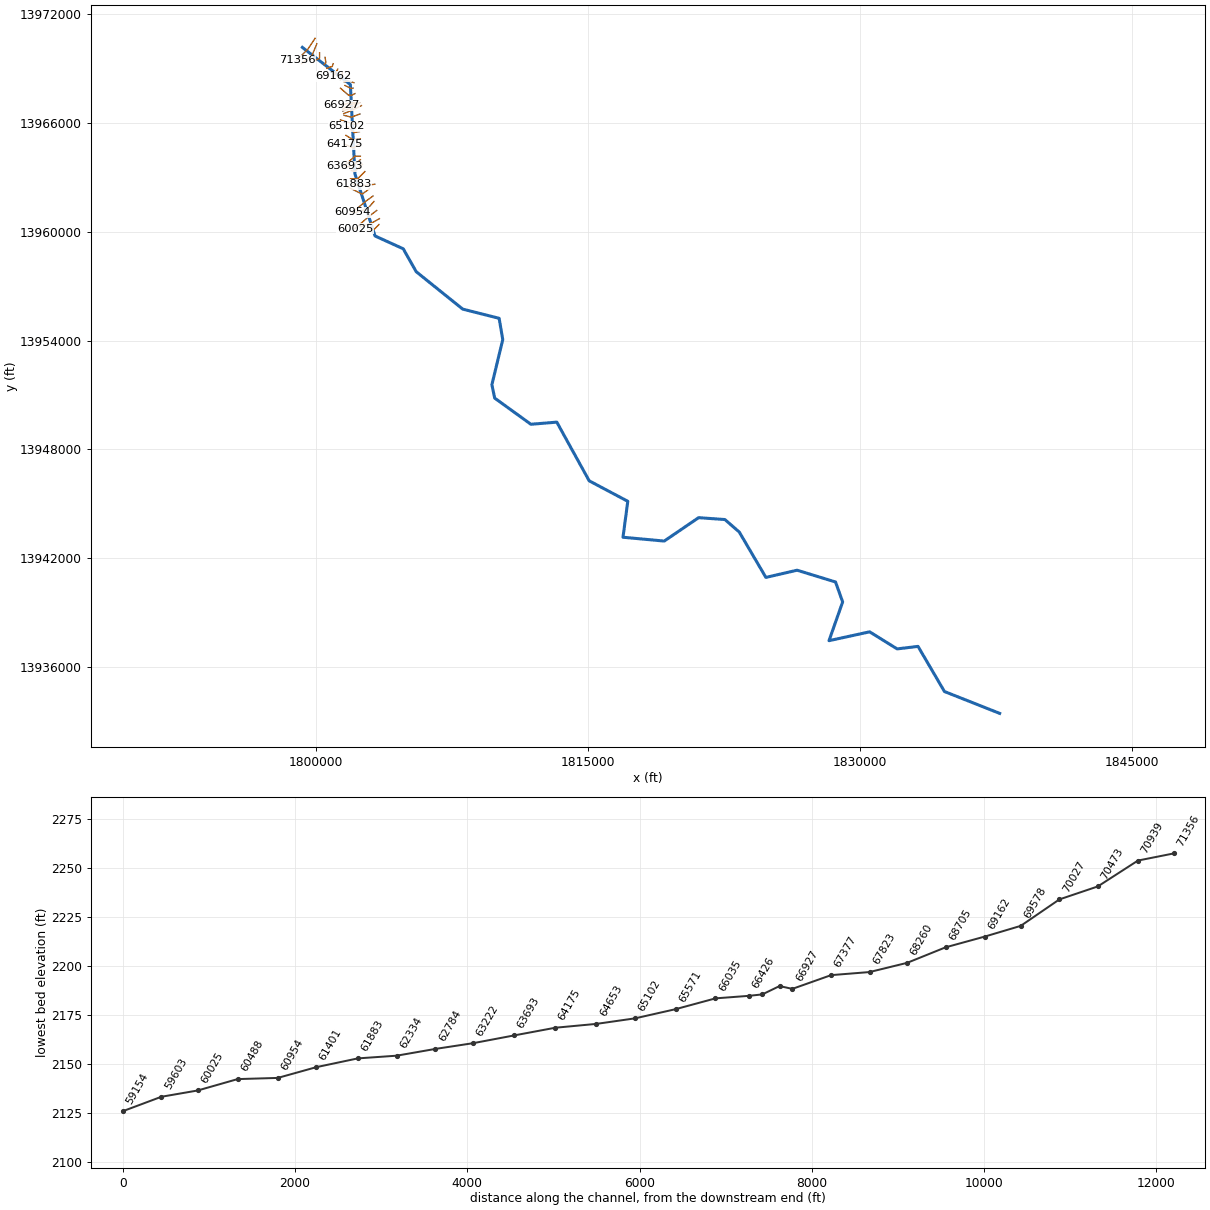
--- Bear Creek 2.prj (project) ---

Proj Title=Bear Creek 2 Base Level Engineering
Current Plan=p01
Default Exp/Contr=0.3,0.1
English Units
Geom File=g01
Flow File=f01
Plan File=p01
Y Axis Title=Elevation
X Axis Title(PF)=Main Channel Distance
X Axis Title(XS)=Station
BEGIN DESCRIPTION:
Bear Creek 2
END DESCRIPTION:
DSS Export Rating Curves= 0
DSS Export Rating Curve Sorted= 0
DSS Export Volume Flow Curves= 0
DXF OffsetX= 0
DXF OffsetY= 0
DXF ScaleX= 1
DXF ScaleY= 10

--- Bear Creek 2.p01 (plan) ---

Plan Title=Multiple Run
Short Identifier=Multiple
Geom File=g01
Flow File=f01
Subcritical Flow
K Sum by GR= 0
Std Step Tol= 0.01
Critical Tol= 0.01
Num of Std Step Trials= 20
Max Error Tol= 0.3
Flow Tol Ratio= 0.001
Split Flow NTrial= 30
Split Flow Tol= 0.02
Split Flow Ratio= 0.02
Log Output Level= 0
Friction Slope Method= 1
Unsteady Friction Slope Method= 2
Unsteady Bridges Friction Slope Method= 1
Parabolic Critical Depth
Global Vel Dist=  1 , 1 , 1
Global Log Level= 0
CheckData=True
Encroach Param= -1, 0, 0, 0
BEGIN DESCRIPTION:
Multiple Run
END DESCRIPTION:

--- Bear Creek 2.f01 (steady flow) ---

Flow Title=Multiple
Number of Profiles=7
Profile Names=10-year,25-year,50-year,1pct_min,100-year,1pct_plu,500-year
River Rch & RM= Bear Creek 2,Reach-1,71356
     258     398     519     328     655    1306    1026
River Rch & RM= Bear Creek 2,Reach-1,70473
    1199    2062    2886    1950    3891    7763    6995
River Rch & RM= Bear Creek 2,Reach-1,66779
    1607    2792    3934    2671    5330   10634    9684
River Rch & RM= Bear Creek 2,Reach-1,59154
    2662    4738    6785    4673    9325   18605   17444
River Rch & RM= Bear Creek 2,Reach-1,53183
    3718    6717    9715    6753   13474   26884   25672
River Rch & RM= Bear Creek 2,Reach-1,51801
    4584    8348   12141    8481   16921   33762   32560
River Rch & RM= Bear Creek 2,Reach-1,48935
    5566   10180   14847   10392   20736   41373   40062
River Rch & RM= Bear Creek 2,Reach-1,42825
    6015   11026   16105   11288   22523   44939   43630
River Rch & RM= Bear Creek 2,Reach-1,40110
    6283   11531   16855   11821   23587   47062   45749
River Rch & RM= Bear Creek 2,Reach-1,38964
    6604   12120   17719   12425   24792   49467   48073
River Rch & RM= Bear Creek 2,Reach-1,34671
    6619   12141   17741   12434   24810   49502   48055
River Rch & RM= Bear Creek 2,Reach-1,31382
    7331   13483   19740   13858   27651   55170   53730
River Rch & RM= Bear Creek 2,Reach-1,24754
    7526   13849   20283   14244   28421   56707   55260
River Rch & RM= Bear Creek 2,Reach-1,21175
    9945   18400   27057   19071   38051   75923   74474
River Rch & RM= Bear Creek 2,Reach-1,16009
   10377   19205   28247   19911   39727   79266   77761
River Rch & RM= Bear Creek 2,Reach-1,8296
   10481   19392   28515   20093   40092   79993   78425
River Rch & RM= Bear Creek 2,Reach-1,5036
   10587   19587   28802   20296   40495   80799   79210
Boundary for River Rch & Prof#=Bear Creek 2,Reach-1,1
Up Type=0
Dn Type=3
Dn Slope=0.005
Boundary for River Rch & Prof#=Bear Creek 2,Reach-1,2
Up Type=0
Dn Type=3
Dn Slope=0.005
Boundary for River Rch & Prof#=Bear Creek 2,Reach-1,3
Up Type=0
Dn Type=3
Dn Slope=0.005
Boundary for River Rch & Prof#=Bear Creek 2,Reach-1,4
Up Type=0
Dn Type=3
Dn Slope=0.005
Boundary for River Rch & Prof#=Bear Creek 2,Reach-1,5
Up Type=0
Dn Type=3
Dn Slope=0.005
Boundary for River Rch & Prof#=Bear Creek 2,Reach-1,6
Up Type=0
Dn Type=3
Dn Slope=0.005
Boundary for River Rch & Prof#=Bear Creek 2,Reach-1,7
Up Type=0
Dn Type=3
Dn Slope=0.005

--- Bear Creek 2.g01 (geometry) ---

Geom Title=Existing Conditions
Program Version=4.10

River Reach=Bear Creek 2    ,Reach-1
Reach XY= 30
        1799275.       13970175.      1801921.45     13968123.53
      1802176.05     13963185.44      1803283.14     13959768.96
      1804838.57     13959061.53       1805551.3     13957798.18
      1808118.54     13955732.74        1810125.       13955225.
       1810325.4       13954050.      1809725.52     13951559.78
      1809880.73     13950822.45      1811876.25     13949378.45
      1813305.38     13949495.47      1815091.65     13946257.47
      1817219.53     13945127.45      1816954.79      13943144.5
      1819228.31     13942933.02        1821125.       13944225.
      1822573.72     13944121.48      1823366.86     13943431.06
      1824833.15     13940928.37       1826554.9     13941325.09
        1828675.       13940675.      1829067.44       13939575.
        1828315.     13937436.24      1830554.83      13937925.3
      1832071.42     13936982.89       1833223.5     13937121.54
      1834680.56     13934630.62        1837725.       13933425.

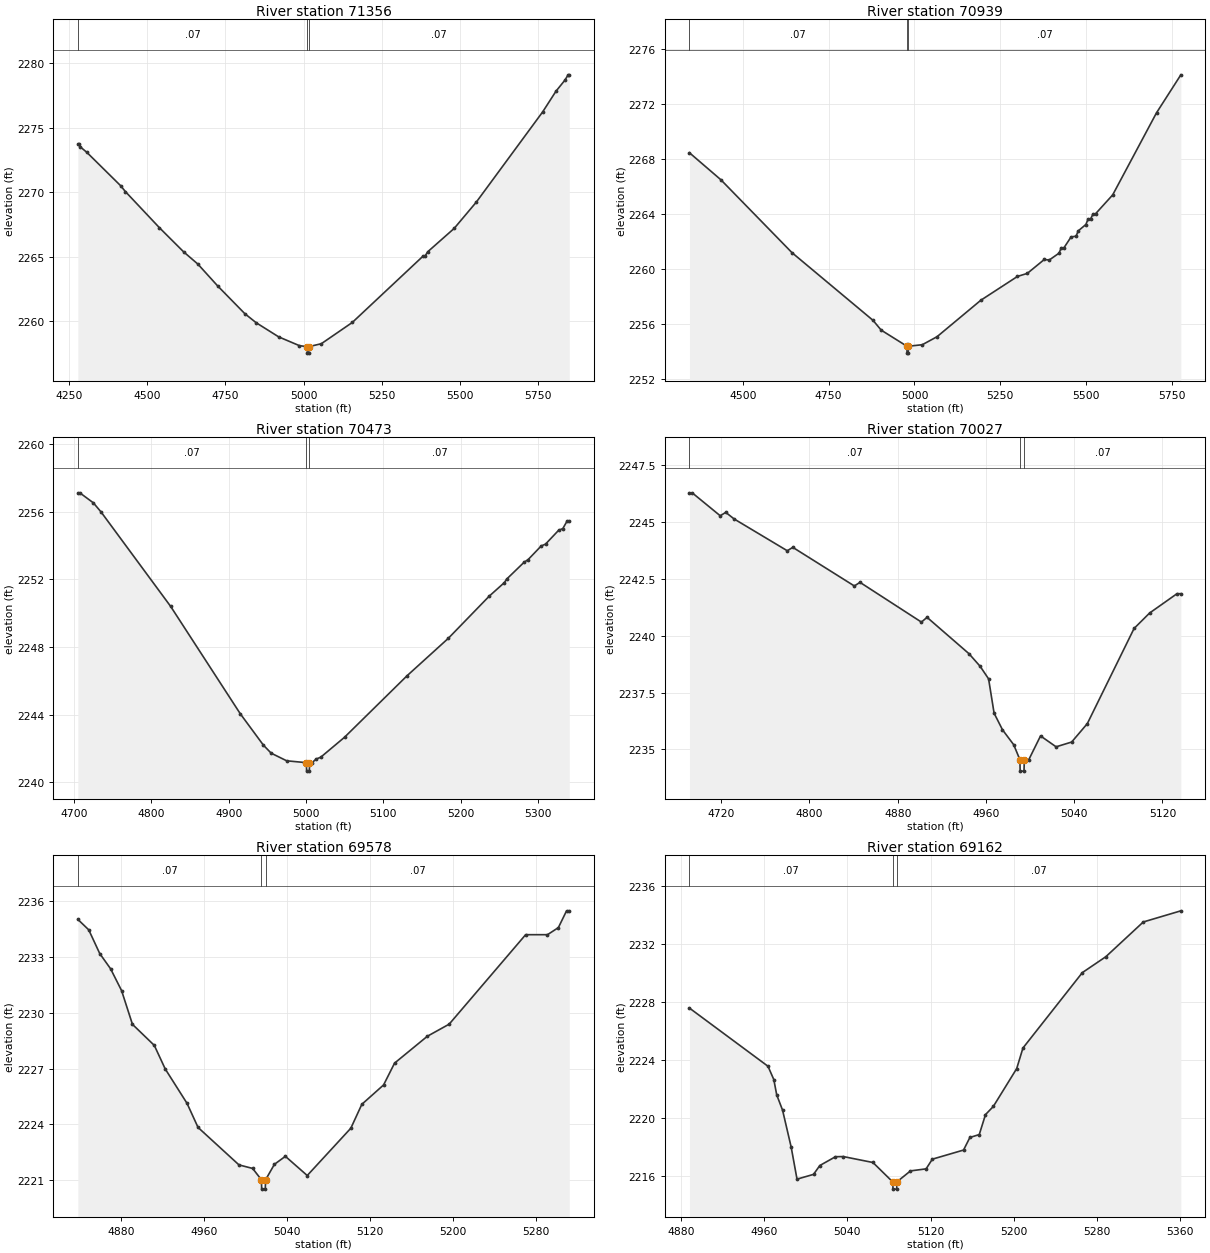
Type RM Length L Ch R = 1 ,71356   ,417,417,417
BEGIN DESCRIPTION:
Bear Creek 2 135.0
END DESCRIPTION:
XS GIS Cut Line= 3
        1799975.     13970675.01        1799575.       13970075.
      1798975.03     13969475.03
#Sta/Elev= 30
  4279.1 2273.72  4282.1 2273.72  4286.6 2273.53  4307.7  2273.1  4415.8 2270.51
  4430.8 2270.06    4539 2267.27  4617.1 2265.38  4662.2 2264.44  4725.3 2262.75
  4812.4 2260.59  4848.5 2259.89  4920.6 2258.79  4986.7 2258.11  5012.4 2258.03
  5012.6 2257.53  5016.1 2257.53  5016.4 2258.03  5056.8 2258.26  5155.8 2259.91
  5382.1 2265.06  5389.1 2265.09  5396.2 2265.38  5481.1  2267.2  5551.8 2269.24
  5763.9 2276.24  5806.3 2277.84  5834.6 2278.69  5845.2 2279.11  5848.7 2279.11
#Mann= 3 ,-1 , 0
  4279.1     .07       0  5012.4     .05       0  5016.4     .07       0
Bank Sta=5012.4,5016.4
XS Rating Curve= 0 ,0
Exp/Cntr=0.3,0.1

Type RM Length L Ch R = 1 ,70939   ,466,466,466
BEGIN DESCRIPTION:
Bear Creek 2 134.0
END DESCRIPTION:
XS GIS Cut Line= 3
      1800074.99     13970374.99        1799825.       13969775.
      1799225.01     13969275.01
#Sta/Elev= 30
  4344.7 2268.43  4436.2 2266.47  4643.1 2261.18  4879.3 2256.26  4903.1 2255.55
  4978.1 2254.38  4978.3 2253.88  4981.8 2253.88  4982.1 2254.38  5022.7 2254.49
  5065.6 2255.07  5193.2 2257.72  5299.9 2259.45  5328.6 2259.67    5378 2260.68
  5392.4 2260.64    5421 2261.14  5427.5 2261.53  5435.3 2261.53  5456.1 2262.32
  5470.5 2262.37    5477 2262.76  5499.1 2263.22  5505.6 2263.61  5513.4 2263.65
  5519.9 2263.98  5527.7 2264.01  5577.2 2265.37  5704.8 2271.33  5775.7 2274.09
#Mann= 3 ,-1 , 0
  4344.7     .07       0  4978.1     .05       0  4982.1     .07       0
Bank Sta=4978.1,4982.1
XS Rating Curve= 0 ,0
Exp/Cntr=0.3,0.1

Type RM Length L Ch R = 1 ,70473   ,446,446,446
BEGIN DESCRIPTION:
Bear Creek 2 133.0
END DESCRIPTION:
XS GIS Cut Line= 3
        1800225.     13969875.04        1800225.       13969575.
      1799925.04     13969425.02
#Sta/Elev= 30
    4705 2257.11  4707.5 2257.11    4725 2256.52    4735 2255.98    4825  2250.4
    4915 2244.06    4945  2242.2    4955 2241.73    4975 2241.28  5000.5 2241.17
  5000.8 2240.67  5004.3 2240.67  5004.5 2241.17  5007.8 2241.17  5013.4 2241.39
    5019 2241.49  5049.8 2242.67  5130.8 2246.31  5183.9 2248.51    5237 2251.01
  5256.6 2251.81  5259.4 2252.01  5281.8    2253  5287.3 2253.17  5304.1 2253.97
  5309.7 2254.08  5326.5 2254.89  5332.1    2255  5337.7 2255.45  5340.4 2255.45
#Mann= 3 ,-1 , 0
    4705     .07       0  5000.5     .05       0  5004.5     .07       0
Bank Sta=5000.5,5004.5
XS Rating Curve= 0 ,0
Exp/Cntr=0.3,0.1

Type RM Length L Ch R = 1 ,70027   ,449,449,449
BEGIN DESCRIPTION:
Bear Creek 2 132.0
END DESCRIPTION:
XS GIS Cut Line= 3
        1800525.     13969624.97        1800575.       13969325.
      1800475.02     13969225.02
#Sta/Elev= 30
  4691.2 2246.29  4693.7 2246.29  4719.1 2245.28  4724.1 2245.43  4731.7 2245.14
  4779.9 2243.74  4784.9 2243.89  4840.7 2242.19  4845.8 2242.35  4901.5  2240.6
  4906.6 2240.81  4944.6 2239.21  4954.8 2238.65  4962.4  2238.1  4967.4 2236.59
    4975 2235.86  4985.2  2235.2  4990.8 2234.54    4991 2234.04  4994.5 2234.04
  4994.8 2234.54  4998.8 2234.54  5009.5 2235.59  5023.6 2235.11  5037.7 2235.32
  5051.9 2236.13  5094.3 2240.32  5108.4    2241  5133.2 2241.85  5136.7 2241.85
#Mann= 3 ,-1 , 0
  4691.2     .07       0  4990.8     .05       0  4994.8     .07       0
Bank Sta=4990.8,4994.8
XS Rating Curve= 0 ,0
Exp/Cntr=0.3,0.1

Type RM Length L Ch R = 1 ,69578   ,416,416,416
BEGIN DESCRIPTION:
Bear Creek 2 131.0
END DESCRIPTION:
XS GIS Cut Line= 3
        1800975.       13969275.        1800925.       13969125.
      1800625.04     13969025.01
#Sta/Elev= 30
  4837.9    2235  4848.4 2234.44    4859 2233.17  4869.5 2232.35  4880.1 2231.18
  4890.6 2229.37  4911.7 2228.24  4922.2 2226.98  4943.3 2225.13  4953.9 2223.84
  4993.4 2221.83  5006.6 2221.64  5015.1 2221.03  5015.3 2220.53  5018.8 2220.53
  5019.1 2221.03  5027.6 2221.86  5038.2 2222.29  5059.3 2221.26  5101.4  2223.8
    5112 2225.08    5133 2226.12  5143.6 2227.29  5175.2 2228.73  5196.3 2229.38
  5270.1 2234.18  5291.2 2234.18  5301.7 2234.56  5309.6 2235.46  5312.2 2235.46
#Mann= 3 ,-1 , 0
  4837.9     .07       0  5015.1     .05       0  5019.1     .07       0
Bank Sta=5015.1,5019.1
XS Rating Curve= 0 ,0
Exp/Cntr=0.3,0.1

Type RM Length L Ch R = 1 ,69162   ,457,457,457
BEGIN DESCRIPTION:
Bear Creek 2 130.0
END DESCRIPTION:
XS GIS Cut Line= 3
        1801225.     13968975.01        1801175.       13968875.
      1800974.98     13968574.97
#Sta/Elev= 30
  4888.2 2227.59  4963.7 2223.57  4969.3 2222.65  4972.1 2221.59  4977.7 2220.54
    4986 2217.98  4991.6 2215.77  5007.5  2216.1  5013.5 2216.71  5028.6 2217.32
  5036.1 2217.33  5064.6 2216.92  5083.6 2215.58  5083.9 2215.08  5087.4 2215.08
  5087.6 2215.58  5100.7 2216.34  5115.7 2216.48  5121.7 2217.15  5151.7 2217.78
  5157.8 2218.65  5166.8 2218.85  5172.8 2220.23  5180.3 2220.79  5202.8 2223.41
  5208.8 2224.83  5265.9 2230.04  5288.5 2231.14  5324.5 2233.54  5360.6 2234.31
#Mann= 3 ,-1 , 0
  4888.2     .07       0  5083.6     .05       0  5087.6     .07       0
Bank Sta=5083.6,5087.6
XS Rating Curve= 0 ,0
Exp/Cntr=0.3,0.1

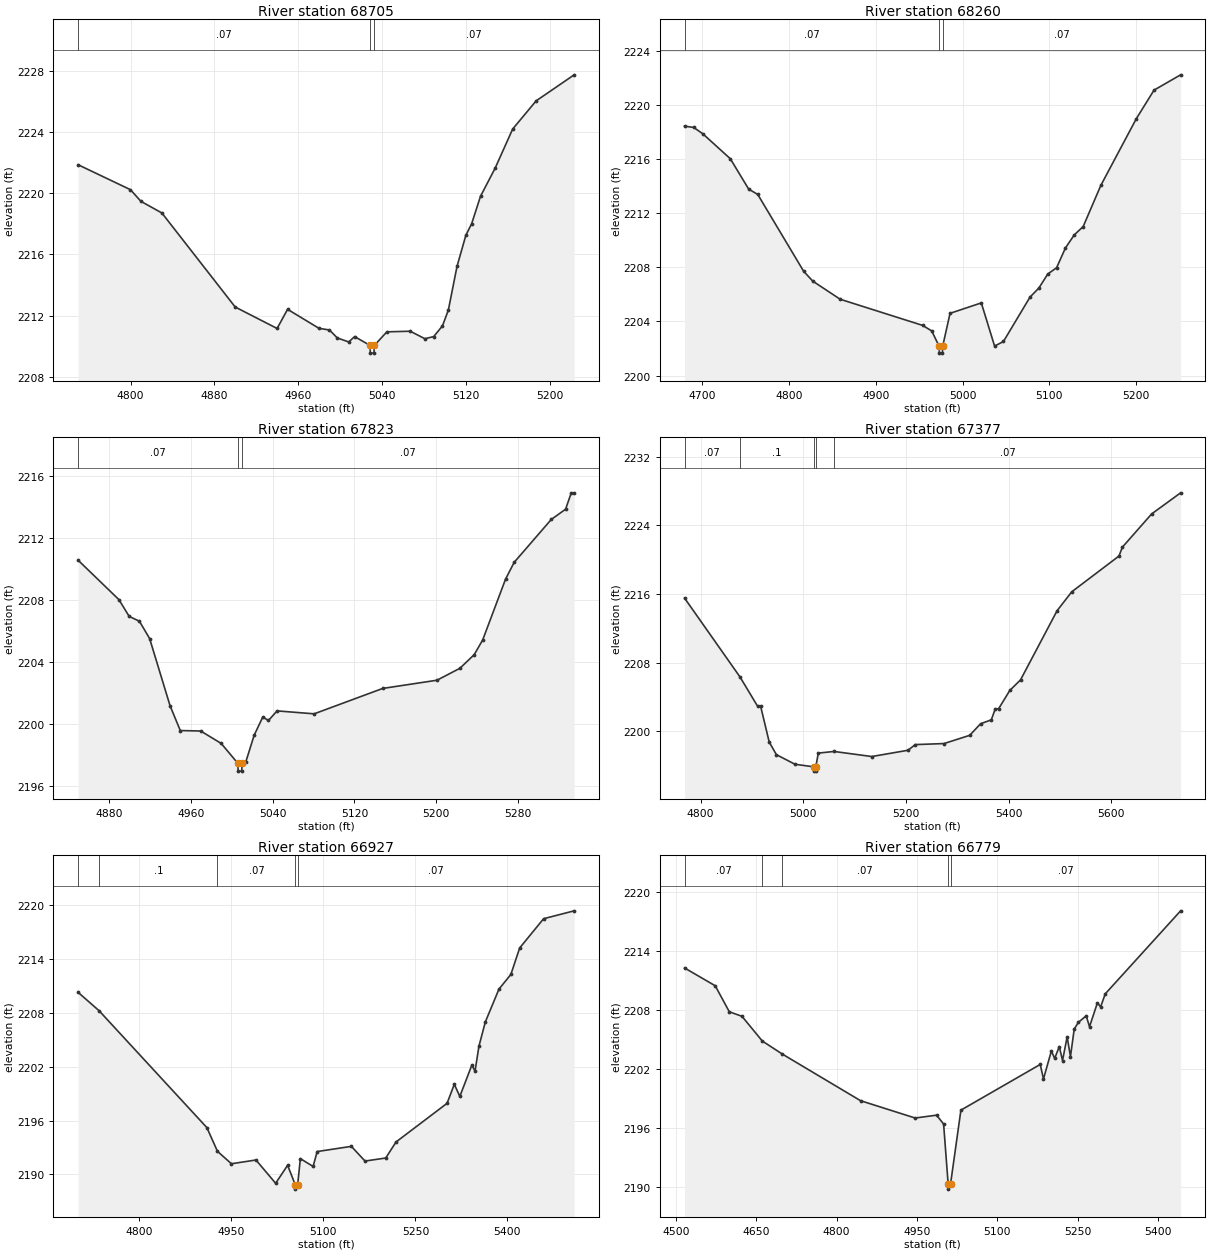
Type RM Length L Ch R = 1 ,68705   ,445,445,445
BEGIN DESCRIPTION:
Bear Creek 2 129.0
END DESCRIPTION:
XS GIS Cut Line= 3
        1801475.     13968825.04        1801475.       13968575.
      1801375.02     13968375.04
#Sta/Elev= 30
  4749.8 2221.86  4799.8 2220.23  4809.8 2219.47  4829.8 2218.71  4899.8 2212.57
  4939.8 2211.17  4949.8 2212.42  4979.8 2211.18  4989.8 2211.07  4997.3 2210.55
  5008.2 2210.29  5013.8 2210.64  5028.6 2210.06  5028.8 2209.56  5032.3 2209.56
  5032.6 2210.06  5044.6 2210.95  5066.9 2210.99  5080.9  2210.5  5089.3 2210.64
  5097.7 2211.34  5103.3 2212.37  5111.6 2215.23    5120 2217.25  5125.6 2218.02
    5134  2219.8    5148 2221.64  5164.7 2224.19  5187.1 2226.03  5223.4 2227.73
#Mann= 3 ,-1 , 0
  4749.8     .07       0  5028.6     .05       0  5032.6     .07       0
Bank Sta=5028.6,5032.6
XS Rating Curve= 0 ,0
Exp/Cntr=0.3,0.1

Type RM Length L Ch R = 1 ,68260   ,437,437,437
BEGIN DESCRIPTION:
Bear Creek 2 128.0
END DESCRIPTION:
XS GIS Cut Line= 3
      1802125.02     13968224.99        1801825.       13968325.
        1801575.       13968275.
#Sta/Elev= 30
  4679.9 2218.43  4690.5 2218.33    4701 2217.86  4732.6 2216.02  4753.7 2213.78
  4764.2 2213.38    4817 2207.71  4827.5 2206.98  4859.1 2205.64    4954 2203.71
  4964.5  2203.3  4973.1 2202.16  4973.3 2201.66  4976.8 2201.66  4977.1 2202.16
  4985.6  2204.6  5021.6 2205.37  5036.9 2202.18  5047.1 2202.52  5077.7  2205.8
  5087.9 2206.47  5098.1  2207.5  5108.3 2207.97  5118.5 2209.43  5128.7  2210.4
  5138.9 2211.01  5159.3 2214.06  5200.1 2218.98  5220.5 2221.09  5251.1 2222.22
#Mann= 3 ,-1 , 0
  4679.9     .07       0  4973.1     .05       0  4977.1     .07       0
Bank Sta=4973.1,4977.1
XS Rating Curve= 0 ,0
Exp/Cntr=0.3,0.1

Type RM Length L Ch R = 1 ,67823   ,446,446,446
BEGIN DESCRIPTION:
Bear Creek 2 127.0
END DESCRIPTION:
XS GIS Cut Line= 3
      1802074.98       13967925.        1801925.       13967925.
      1801624.99     13968075.01
#Sta/Elev= 30
  4849.6 2210.57  4889.6 2208.02  4899.6 2206.94  4909.6 2206.63  4919.6 2205.51
  4939.6 2201.17  4949.6 2199.57  4969.6 2199.54  4989.6 2198.74    5006 2197.45
  5006.2 2196.95  5009.7 2196.95    5010 2197.45  5013.6 2197.52  5021.9 2199.27
  5030.3 2200.44  5035.9 2200.22  5044.3 2200.84  5080.6 2200.65  5147.7 2202.29
  5200.8 2202.82  5223.2 2203.59  5237.2 2204.47  5245.5 2205.42  5267.9 2209.35
  5276.3 2210.43  5312.6  2213.2  5326.6 2213.86  5332.2 2214.92    5335 2214.92
#Mann= 3 ,-1 , 0
  4849.6     .07       0    5006     .05       0    5010     .07       0
Bank Sta=5006,5010
XS Rating Curve= 0 ,0
Exp/Cntr=0.3,0.1

Type RM Length L Ch R = 1 ,67377   ,450,450,450
BEGIN DESCRIPTION:
Bear Creek 2 126.0
END DESCRIPTION:
XS GIS Cut Line= 4
      1802174.98     13967624.99        1801975.       13967525.
      1801810.02     13967546.49        1801375.       13967925.
#Sta/Elev= 30
  4768.6 2215.53  4876.6 2206.35  4911.1 2202.92  4916.7 2202.97  4933.5 2198.78
  4947.5  2197.3  4983.8 2196.18  5020.4 2195.88  5020.7 2195.38  5024.2 2195.38
  5024.4 2195.88  5029.2 2197.48  5059.9 2197.67  5133.4 2197.08    5204 2197.81
  5218.2 2198.47  5274.2 2198.59  5324.3 2199.55  5345.4  2200.9  5366.3 2201.35
  5373.9 2202.61  5380.6 2202.65  5402.4 2204.78  5423.3 2206.01  5494.5 2214.06
    5523 2216.26  5615.1 2220.43  5621.7 2221.46  5678.7 2225.33  5735.2 2227.79
#Mann= 5 ,-1 , 0
  4768.6     .07       0  4876.6      .1       0  5020.4     .05       0
  5024.4      .1       0  5059.9     .07       0
Bank Sta=5020.4,5024.4
XS Rating Curve= 0 ,0
Exp/Cntr=0.3,0.1

Type RM Length L Ch R = 1 ,66927   ,148,148,148
BEGIN DESCRIPTION:
Bear Creek 2 125.0
END DESCRIPTION:
XS GIS Cut Line= 3
      1802225.05       13967125.        1801925.       13967125.
      1801435.81     13966985.27
#Sta/Elev= 30
    4700 2210.31  4734.2 2208.26    4910 2195.22  4927.2 2192.58    4950 2191.19
    4990 2191.61  5022.1 2189.01  5041.6 2191.02    5054 2188.86  5054.2 2188.36
    5058 2188.86  5062.4 2191.76  5083.2 2190.89  5089.8 2192.55  5145.6 2193.13
  5167.8 2191.49  5201.6 2191.83  5218.4 2193.62  5301.6 2197.93  5313.4 2200.05
  5322.4  2198.7    5342 2202.19  5347.2 2201.52  5353.6 2204.31    5364 2207.01
  5386.2 2210.67  5405.6  2212.3    5420 2215.26    5459 2218.52  5508.8  2219.4
#Mann= 5 ,-1 , 0
    4700     .07       0  4734.2      .1       0  4927.2     .07       0
    5054     .05       0    5058     .07       0
Bank Sta=5054,5058
XS Rating Curve= 0 ,0
Exp/Cntr=0.3,0.1

Type RM Length L Ch R = 1 ,66779   ,201,201,201
BEGIN DESCRIPTION:
Bear Creek 2 124.2
END DESCRIPTION:
XS GIS Cut Line= 4
       1802346.8     13967101.59      1801910.65     13967010.45
      1801780.44     13966958.37      1801503.55     13966759.35
#Sta/Elev= 30
  4515.8 2212.26  4573.1 2210.45  4599.4 2207.81  4623.1 2207.35    4661 2204.84
  4698.6 2203.51  4844.6 2198.78  4946.7 2197.02  4986.6 2197.31  4999.8 2196.41
  5008.3  2190.3  5008.6  2189.8  5012.7  2190.3  5032.1 2197.82  5180.3 2202.46
  5186.4 2200.99  5201.1 2203.82  5207.3 2203.08  5215.9 2204.27    5222 2202.86
  5230.6 2205.26  5236.8 2203.26  5243.8 2206.05  5251.5 2206.73  5266.2  2207.4
  5272.4 2206.29  5287.1 2208.71  5293.2 2208.31  5301.8 2209.63  5442.6 2218.06
#Mann= 5 ,-1 , 0
  4515.8     .07       0    4661      .1       0  4698.6     .07       0
  5008.3     .05       0  5012.7     .07       0
Bank Sta=5008.3,5012.7
XS Rating Curve= 0 ,0
Exp/Cntr=0.3,0.1

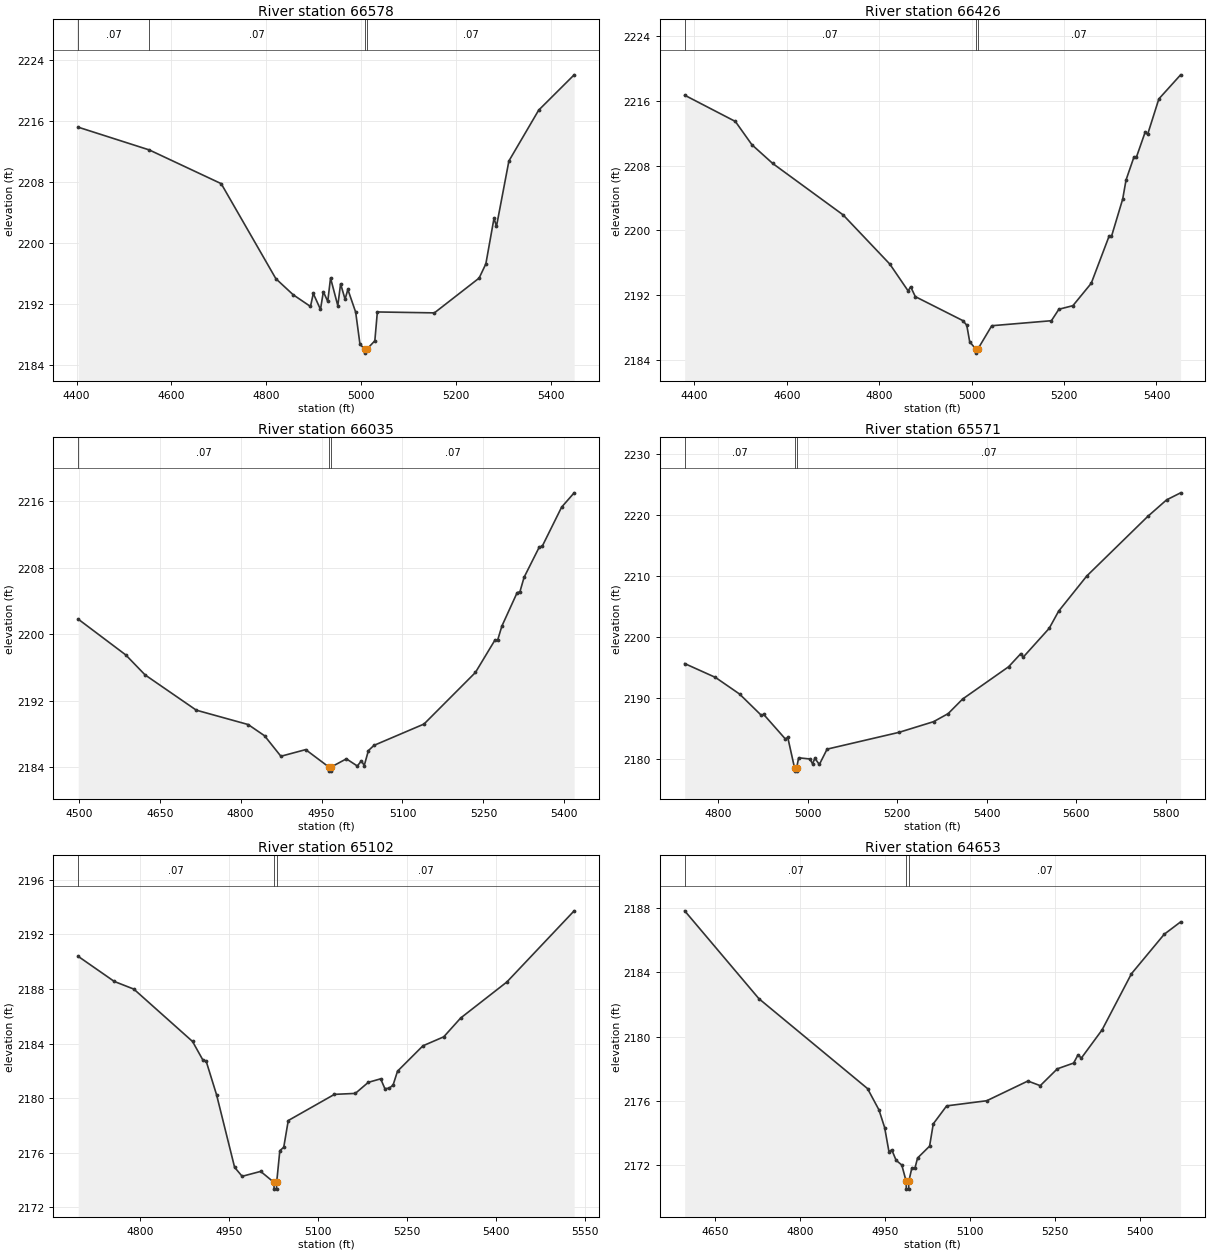
Type RM Length L Ch R = 1 ,66578   ,152,152,152
BEGIN DESCRIPTION:
Bear Creek 2 124.1
END DESCRIPTION:
XS GIS Cut Line= 3
      1802431.31     13967123.17      1801949.11      13966818.9
      1801498.69     13966666.12
#Sta/Elev= 30
  4403.5 2215.23  4553.4 2212.24    4705 2207.81  4820.3 2195.32  4856.8 2193.21
  4893.3 2191.67  4899.2 2193.38  4914.4 2191.28  4920.4 2193.61  4929.7 2192.34
  4935.6 2195.41  4950.9 2191.78  4956.8 2194.65  4966.2 2192.62  4972.1 2193.91
  4988.6 2190.92  4997.6 2186.73  5007.5 2186.04  5007.8 2185.54  5011.9 2186.04
    5029 2187.16  5034.3 2190.95  5154.6 2190.83  5248.9  2195.4  5263.1 2197.27
  5280.3 2203.26  5285.5  2202.2  5311.7 2210.79  5374.5 2217.47  5449.3 2222.11
#Mann= 4 ,-1 , 0
  4403.5     .07       0  4553.4     .07       0  5007.5     .05       0
  5011.9     .07       0
Bank Sta=5007.5,5011.9
XS Rating Curve= 0 ,0
Exp/Cntr=0.3,0.1

Type RM Length L Ch R = 1 ,66426   ,391,391,391
BEGIN DESCRIPTION:
Bear Creek 2 124.0
END DESCRIPTION:
XS GIS Cut Line= 3
      1802533.59     13966962.43       1801978.4      13966691.6
      1801555.32      13966522.9
#Sta/Elev= 30
  4379.1 2216.73  4488.8 2213.48  4524.6  2210.6  4569.7 2208.28  4721.8 2201.93
  4823.1 2195.83  4862.6 2192.52  4868.1 2193.03  4878.2 2191.81  4980.8 2188.85
  4989.5 2188.28  4995.9 2186.22  5009.1 2185.32  5009.4 2184.82  5013.5 2185.32
  5043.6 2188.21  5172.7 2188.83  5188.9 2190.25  5219.2 2190.69  5258.9 2193.46
  5297.3 2199.26  5302.7 2199.26    5327 2203.89  5334.2 2206.24  5351.3 2209.08
  5356.6 2209.06  5375.5 2212.15  5380.9 2211.88  5405.2 2216.27  5452.3 2219.25
#Mann= 3 ,-1 , 0
  4379.1     .07       0  5009.1     .05       0  5013.5     .07       0
Bank Sta=5009.1,5013.5
XS Rating Curve= 0 ,0
Exp/Cntr=0.3,0.1

Type RM Length L Ch R = 1 ,66035   ,464,464,464
BEGIN DESCRIPTION:
Bear Creek 2 123.0
END DESCRIPTION:
XS GIS Cut Line= 3
      1802450.23     13966501.61        1801975.       13966325.
        1801575.       13966425.
#Sta/Elev= 30
  4498.9 2201.82  4587.1 2197.51  4622.8 2195.11  4717.8 2190.86  4813.9 2189.13
  4844.3 2187.78  4874.6 2185.31  4920.5 2186.11  4963.4 2184.02  4963.8 2183.52
  4967.6 2183.52  4967.9 2184.02    4996    2185  5016.2 2184.14  5023.9 2184.76
  5029.1 2184.19  5036.8 2185.99  5047.1 2186.62  5139.9 2189.19  5235.2  2195.4
  5271.3 2199.29  5276.5 2199.32  5284.2 2200.98  5312.5 2205.01  5317.7 2205.12
  5325.4 2206.86  5353.8 2210.53  5358.9 2210.58    5395 2215.31  5418.2 2217.03
#Mann= 3 ,-1 , 0
  4498.9     .07       0  4963.4     .05       0  4967.9     .07       0
Bank Sta=4963.4,4967.9
XS Rating Curve= 0 ,0
Exp/Cntr=0.3,0.1

Type RM Length L Ch R = 1 ,65571   ,469,469,469
BEGIN DESCRIPTION:
Bear Creek 2 122.0
END DESCRIPTION:
XS GIS Cut Line= 3
      1802424.99     13966024.99        1802175.       13965925.
        1801375.       13966175.
#Sta/Elev= 30
  4725.5 2195.65  4794.1 2193.38    4848 2190.65  4896.5 2187.16  4901.8 2187.31
  4950.3 2183.27  4955.7 2183.52  4970.9 2178.49  4971.3 2177.99  4975.2 2177.99
  4975.5 2178.49  4979.9 2180.18  5005.2 2179.98    5011 2179.19  5016.2  2180.1
  5026.2 2179.08  5043.5  2181.6  5204.3 2184.36  5281.3 2186.11  5313.8 2187.43
  5346.2 2189.83  5448.9 2195.13  5476.2 2197.29  5481.4  2196.7  5539.5 2201.44
  5560.5 2204.25  5623.4 2210.03  5759.6 2219.81  5801.5 2222.52  5832.9 2223.68
#Mann= 3 ,-1 , 0
  4725.5     .07       0  4970.9     .05       0  4975.5     .07       0
Bank Sta=4970.9,4975.5
XS Rating Curve= 0 ,0
Exp/Cntr=0.3,0.1

Type RM Length L Ch R = 1 ,65102   ,449,449,449
BEGIN DESCRIPTION:
Bear Creek 2 121.0
END DESCRIPTION:
XS GIS Cut Line= 3
      1802424.95     13965524.99        1802125.       13965475.
        1801725.       13965825.
#Sta/Elev= 30
    4696 2190.39  4756.8 2188.55  4789.7 2187.99  4888.6 2184.15  4906.3 2182.77
  4911.4 2182.73  4929.1 2180.24  4959.5 2174.92  4972.2 2174.26  5003.4 2174.62
  5025.7 2173.82  5026.1 2173.32  5030.1 2173.32  5030.4 2173.82  5035.7 2176.14
  5042.3 2176.39  5049.9 2178.35  5127.7 2180.27  5162.9 2180.34  5184.7 2181.15
  5205.6 2181.41  5212.7 2180.69  5219.8 2180.72  5226.5 2180.95    5234 2181.97
  5276.8 2183.83  5311.9 2184.49  5340.4 2185.87  5418.2 2188.51  5531.6 2193.73
#Mann= 3 ,-1 , 0
    4696     .07       0  5025.7     .05       0  5030.4     .07       0
Bank Sta=5025.7,5030.4
XS Rating Curve= 0 ,0
Exp/Cntr=0.3,0.1

Type RM Length L Ch R = 1 ,64653   ,478,478,478
BEGIN DESCRIPTION:
Bear Creek 2 120.0
END DESCRIPTION:
XS GIS Cut Line= 3
      1802475.01       13965125.        1802075.       13965075.
      1801675.02     13965324.99
#Sta/Elev= 30
  4596.4 2187.84  4727.4 2182.36  4918.9 2176.76  4939.1 2175.43  4949.1 2174.33
  4956.7 2172.83  4961.7 2172.94  4969.3 2172.29  4979.4 2171.99    4987 2170.99
  4987.4 2170.49  4991.5 2170.49  4991.8 2170.99    4997 2171.79  5002.5 2171.79
  5007.2 2172.43  5028.4 2173.17  5034.9 2174.56  5058.5 2175.68  5129.2    2176
  5201.8 2177.23  5223.6 2176.94  5253.7 2177.99  5282.5 2178.35  5290.2 2178.86
  5296.1 2178.66  5332.7 2180.42  5384.5 2183.92  5442.3 2186.38  5471.2 2187.15
#Mann= 3 ,-1 , 0
  4596.4     .07       0    4987     .05       0  4991.8     .07       0
Bank Sta=4987,4991.8
XS Rating Curve= 0 ,0
Exp/Cntr=0.3,0.1

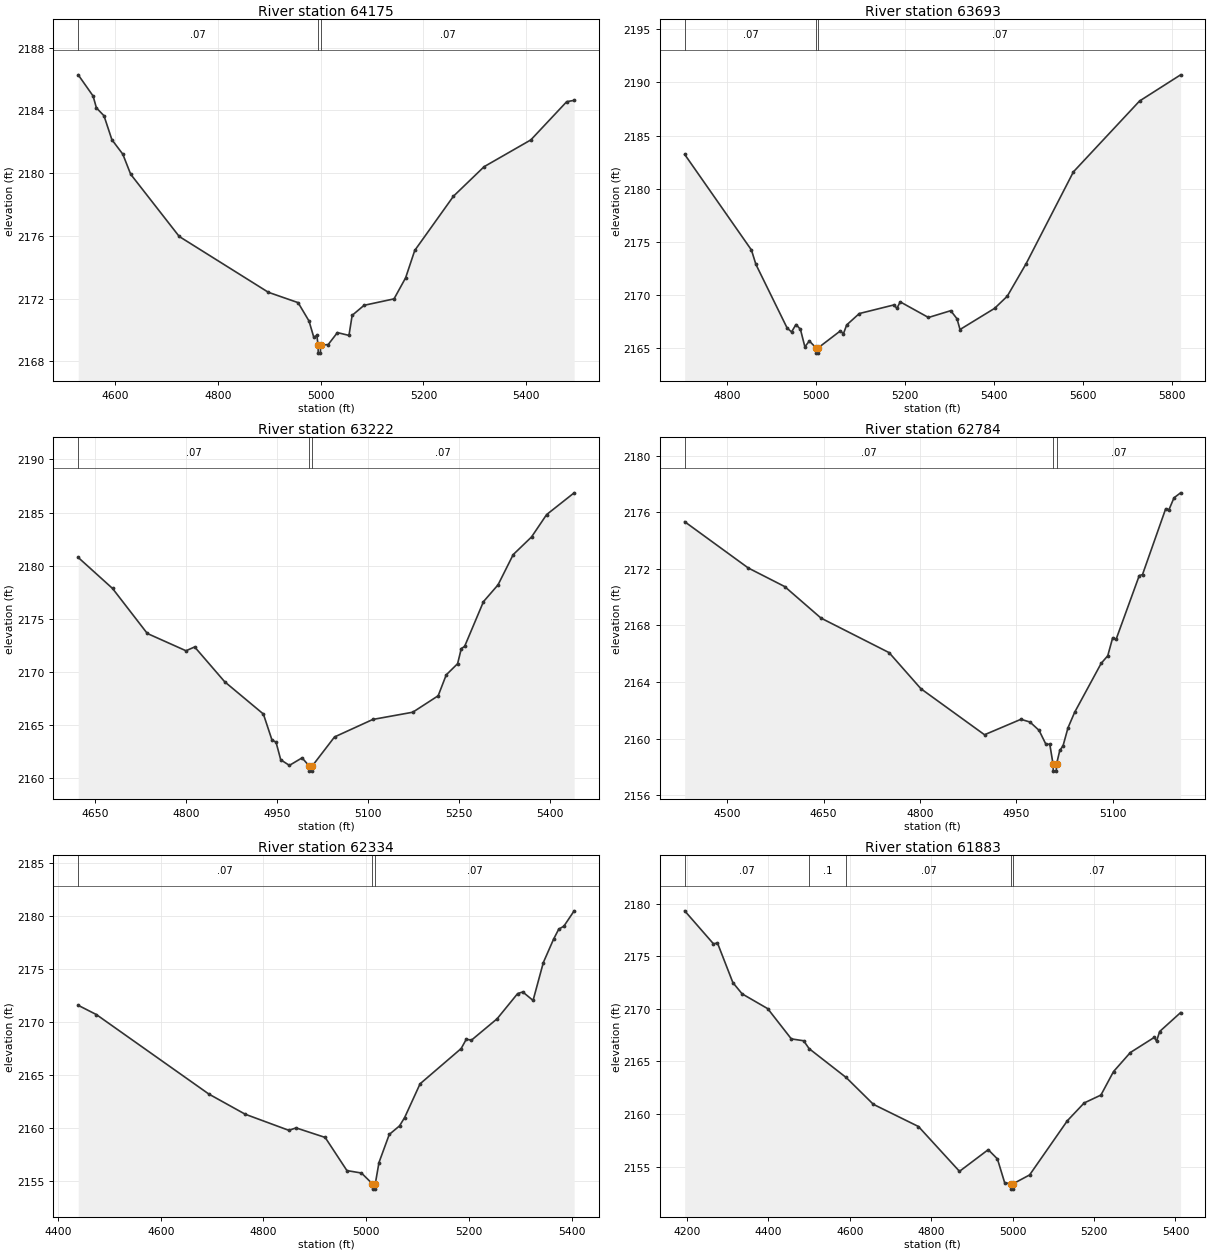
Type RM Length L Ch R = 1 ,64175   ,482,482,482
BEGIN DESCRIPTION:
Bear Creek 2 119.0
END DESCRIPTION:
XS GIS Cut Line= 3
      1802475.01     13964875.01        1802075.       13964625.
      1801624.96     13964825.02
#Sta/Elev= 30
  4528.7 2186.27  4557.6 2184.92  4564.1 2184.16  4578.8 2183.66  4594.2 2182.13
  4615.4 2181.21  4630.7 2179.93  4725.1 2175.96  4898.4  2172.4  4956.2 2171.74
  4977.4 2170.57  4986.8 2169.52  4992.7 2169.66    4995 2169.02  4995.4 2168.52
  4999.6 2168.52  4999.9 2169.02  5014.8 2169.07  5032.6 2169.83  5055.1 2169.65
  5061.3 2170.93  5084.5 2171.57  5142.7 2171.98  5165.2 2173.32    5183 2175.07
  5258.3 2178.53  5317.8 2180.41  5408.7 2182.12  5478.5 2184.56  5492.9 2184.64
#Mann= 3 ,-1 , 0
  4528.7     .07       0    4995     .05       0  4999.9     .07       0
Bank Sta=4995,4999.9
XS Rating Curve= 0 ,0
Exp/Cntr=0.3,0.1

Type RM Length L Ch R = 1 ,63693   ,471,471,471
BEGIN DESCRIPTION:
Bear Creek 2 118.0
END DESCRIPTION:
XS GIS Cut Line= 3
      1802475.05       13964175.        1802175.       13964175.
      1801574.99     13963624.99
#Sta/Elev= 30
    4705 2183.24    4855 2174.25    4865  2172.9    4935 2166.93    4945 2166.55
    4955 2167.25    4965  2166.8    4975 2165.15    4985  2165.7    5000 2165.06
  5000.4 2164.56  5004.6 2164.56    5005 2165.06  5054.7 2166.65  5061.5 2166.37
  5068.9 2167.21  5097.2 2168.28  5174.9 2169.09  5181.7 2168.77  5189.1 2169.38
  5252.6 2167.91  5302.6 2168.55  5316.7 2167.79  5323.5 2166.78  5401.2 2168.77
  5429.6 2169.91  5472.1 2172.98  5578.2  2181.6  5726.8 2188.26    5819 2190.72
#Mann= 3 ,-1 , 0
    4705     .07       0    5000     .05       0    5005     .07       0
Bank Sta=5000,5005
XS Rating Curve= 0 ,0
Exp/Cntr=0.3,0.1

Type RM Length L Ch R = 1 ,63222   ,438,438,438
BEGIN DESCRIPTION:
Bear Creek 2 117.0
END DESCRIPTION:
XS GIS Cut Line= 3
      1802475.01     13963975.01        1802175.       13963725.
      1801775.03     13963575.01
#Sta/Elev= 30
    4622 2180.77  4678.6 2177.85  4735.9 2173.61  4799.7 2171.98    4814 2172.34
  4863.5 2169.06  4927.3 2166.02  4941.6 2163.55  4948.1 2163.38  4955.9 2161.71
  4970.2 2161.18  4991.1 2161.89  5002.6 2161.14  5003.1 2160.64  5007.7 2160.64
  5008.1 2161.14  5044.6 2163.86  5107.8 2165.51  5173.6 2166.19  5215.5 2167.74
  5228.8 2169.71  5247.5 2170.76  5253.7 2172.19  5259.1 2172.39  5290.2 2176.61
  5314.2 2178.19  5339.2 2181.04  5369.4  2182.7  5394.3 2184.81  5439.7 2186.86
#Mann= 3 ,-1 , 0
    4622     .07       0  5002.6     .05       0  5008.1     .07       0
Bank Sta=5002.6,5008.1
XS Rating Curve= 0 ,0
Exp/Cntr=0.3,0.1

Type RM Length L Ch R = 1 ,62784   ,450,450,450
BEGIN DESCRIPTION:
Bear Creek 2 116.0
END DESCRIPTION:
XS GIS Cut Line= 3
      1802575.03     13963725.03        1802175.       13963325.
      1801974.98     13963375.01
#Sta/Elev= 30
  4433.9 2175.33  4532.9 2172.06  4589.5 2170.75  4646.1 2168.52  4752.1 2166.08
  4801.6 2163.53  4900.6 2160.28  4957.2 2161.37  4971.3 2161.18  4985.5 2160.59
  4996.1 2159.61  5002.2 2159.61  5007.2 2158.21  5007.6 2157.71  5012.2 2157.71
  5012.7 2158.21  5017.7 2159.17  5022.8  2159.5  5030.5 2160.77  5040.9 2161.87
  5082.1 2165.32  5092.4 2165.86  5100.1 2167.14  5105.3 2167.01  5141.4 2171.52
  5146.5  2171.6  5182.6 2176.25  5187.7 2176.18  5195.5 2177.02  5205.8 2177.37
#Mann= 3 ,-1 , 0
  4433.9     .07       0  5007.2     .05       0  5012.7     .07       0
Bank Sta=5007.2,5012.7
XS Rating Curve= 0 ,0
Exp/Cntr=0.3,0.1

Type RM Length L Ch R = 1 ,62334   ,451,451,451
BEGIN DESCRIPTION:
Bear Creek 2 115.0
END DESCRIPTION:
XS GIS Cut Line= 3
      1802724.97     13963324.97        1802325.       13962925.
      1801925.05       13962925.
#Sta/Elev= 30
  4439.4  2171.6  4474.7 2170.73  4693.9 2163.22  4764.6 2161.32  4849.5  2159.8
  4863.6 2160.03  4920.2 2159.13  4962.6    2156  4990.9 2155.77  5012.2 2154.75
  5012.7 2154.25  5017.4 2154.25  5017.8 2154.75    5025 2156.76    5045 2159.41
    5065 2160.22    5075 2161.01    5105 2164.19    5185 2167.52    5195  2168.4
    5205 2168.31    5255 2170.33    5295 2172.71    5305 2172.86    5325 2172.06
    5345 2175.64    5365 2177.85    5375 2178.79    5385 2179.07    5405 2180.52
#Mann= 3 ,-1 , 0
  4439.4     .07       0  5012.2     .05       0  5017.8     .07       0
Bank Sta=5012.2,5017.8
XS Rating Curve= 0 ,0
Exp/Cntr=0.3,0.1

Type RM Length L Ch R = 1 ,61883   ,482,482,482
BEGIN DESCRIPTION:
Bear Creek 2 114.0
END DESCRIPTION:
XS GIS Cut Line= 3
      1803275.01       13962625.        1802475.       13962525.
      1802075.04     13962624.99
#Sta/Elev= 30
  4194.1 2179.32  4264.7 2176.19  4274.7 2176.26  4312.5  2172.5  4335.2 2171.43
  4398.2 2170.02  4456.1 2167.15  4486.4 2166.97  4499.9 2166.22  4590.8 2163.48
  4657.7 2160.93  4768.5 2158.82  4869.3 2154.56  4939.9 2156.62  4962.5 2155.74
  4980.2 2153.49    4995 2153.37  4995.5 2152.87  5000.2 2152.87  5000.6 2153.37
  5041.6 2154.22  5134.3 2159.37  5175.6 2161.06  5216.8 2161.81  5247.7 2164.04
    5289 2165.85  5348.2  2167.3  5353.4 2166.93  5361.1 2167.85  5412.6 2169.65
#Mann= 5 ,-1 , 0
  4194.1     .07       0  4499.9      .1       0  4590.8     .07       0
    4995     .05       0  5000.6     .07       0
Bank Sta=4995,5000.6
XS Rating Curve= 0 ,0
Exp/Cntr=0.3,0.1

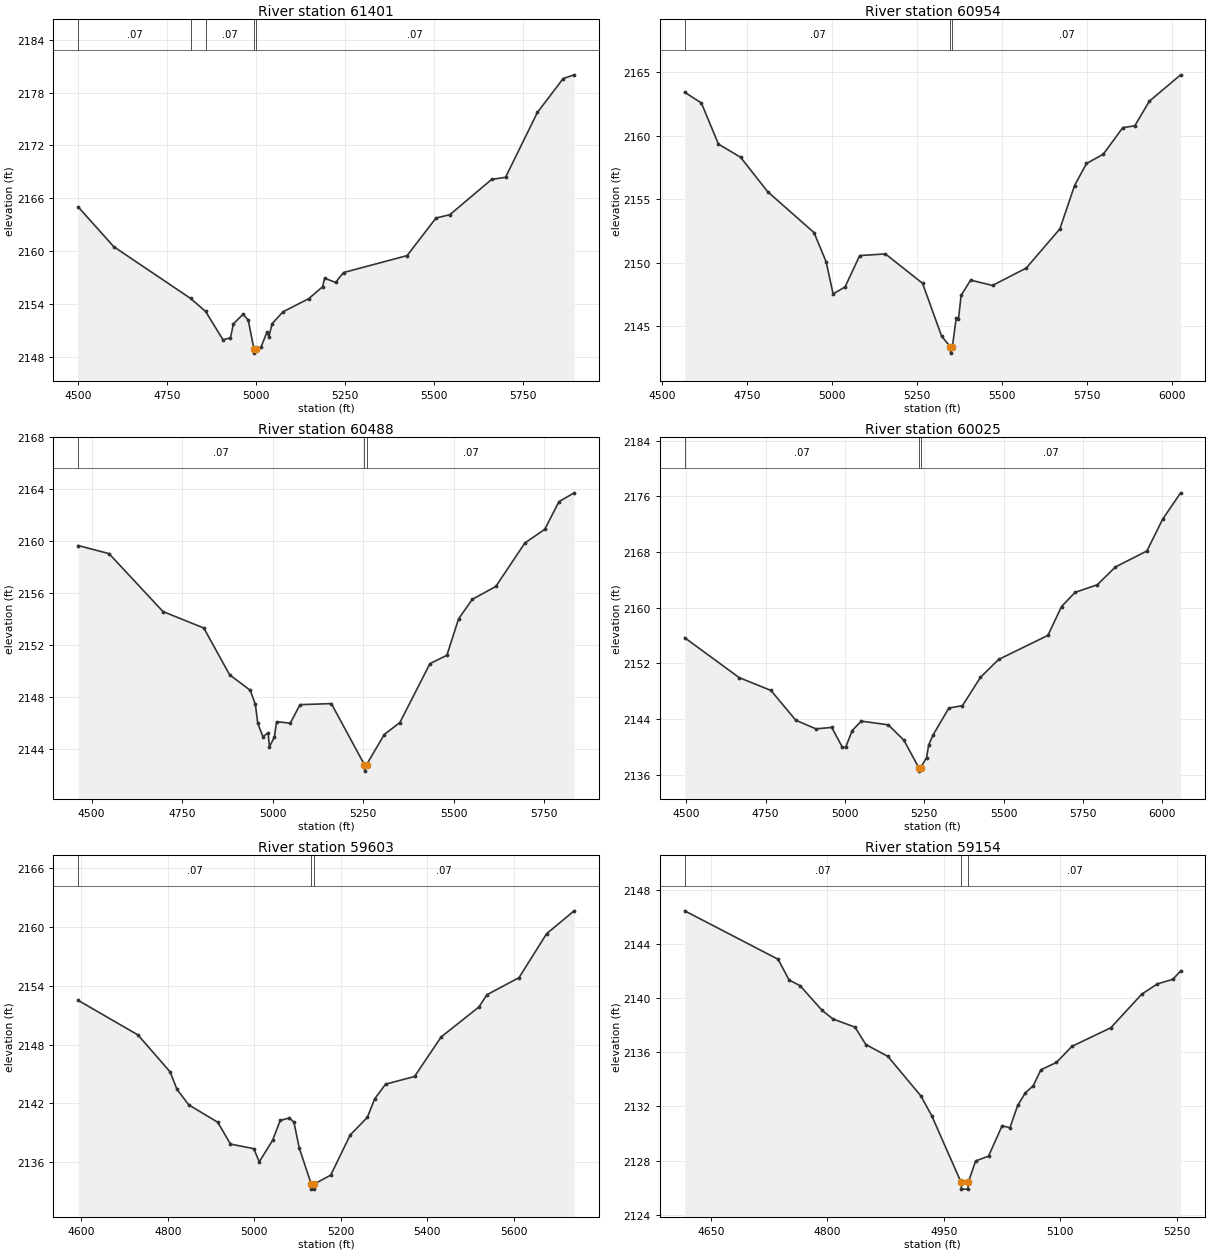
Type RM Length L Ch R = 1 ,61401   ,447,447,447
BEGIN DESCRIPTION:
Bear Creek 2 113.0
END DESCRIPTION:
XS GIS Cut Line= 3
      1802974.97     13962374.97        1802575.       13962075.
      1801774.99     13962475.01
#Sta/Elev= 30
    4500 2165.01    4600 2160.49  4815.9 2154.61  4858.2 2153.13  4907.2  2149.9
  4928.1 2150.14  4936.4 2151.72  4963.5 2152.81  4978.1 2152.14  4993.9 2148.89
  4994.4 2148.39  4999.7 2148.89  5013.9 2149.06  5030.7 2150.78  5036.3 2150.25
  5044.7 2151.71  5075.4 2153.08  5148.1 2154.58  5187.2 2155.94  5192.8  2156.9
  5223.6 2156.43  5245.9 2157.55  5424.8 2159.48  5505.9 2163.75    5545 2164.13
  5662.4 2168.14  5701.5 2168.38    5791 2175.75  5863.6 2179.61  5894.4 2180.03
#Mann= 5 ,-1 , 0
    4500     .07       0  4815.9      .1       0  4858.2     .07       0
  4993.9     .05       0  4999.7     .07       0
Bank Sta=4993.9,4999.7
XS Rating Curve= 0 ,0
Exp/Cntr=0.3,0.1

Type RM Length L Ch R = 1 ,60954   ,466,466,466
BEGIN DESCRIPTION:
Bear Creek 2 112.0
END DESCRIPTION:
XS GIS Cut Line= 3
      1803174.98     13961974.99        1802825.       13961725.
      1802024.98     13961074.98
#Sta/Elev= 30
  4565.5 2163.41  4614.6 2162.57    4665 2159.33  4730.2  2158.3    4810 2155.59
  4946.4 2152.38  4982.1 2150.09  5002.8 2147.55    5038 2148.11  5081.1 2150.57
  5156.7  2150.7  5266.2 2148.39  5322.4 2144.23  5348.2  2143.4  5348.7  2142.9
  5354.1  2143.4  5365.5 2145.69    5372 2145.58  5379.9 2147.45  5407.9 2148.64
  5472.3 2148.22  5571.7 2149.59  5670.8 2152.67  5713.9 2156.07  5749.1 2157.81
  5798.7 2158.54  5856.1 2160.63  5891.3 2160.77  5934.4 2162.71  6026.4 2164.78
#Mann= 3 ,-1 , 0
  4565.5     .07       0  5348.2     .05       0  5354.1     .07       0
Bank Sta=5348.2,5354.1
XS Rating Curve= 0 ,0
Exp/Cntr=0.3,0.1

Type RM Length L Ch R = 1 ,60488   ,463,463,463
BEGIN DESCRIPTION:
Bear Creek 2 111.0
END DESCRIPTION:
XS GIS Cut Line= 3
        1803225.       13961675.        1802875.       13961275.
      1802074.97     13961024.99
#Sta/Elev= 30
  4462.8 2159.67  4547.8 2159.05  4696.8 2154.59  4809.7 2153.32  4880.9 2149.72
  4937.8 2148.53  4952.1 2147.44  4958.7 2145.98    4973 2144.95  4987.2 2145.26
    4991 2144.18  5004.8 2144.93  5010.6 2146.11  5048.3 2145.99  5075.5 2147.42
  5161.9  2147.5  5253.2  2142.8  5253.7  2142.3  5259.2  2142.8  5308.1 2145.12
  5351.1 2146.04  5434.3 2150.58    5481 2151.22  5513.4 2154.03  5551.2 2155.53
  5616.1 2156.52  5696.3 2159.86  5751.3 2160.92  5790.6 2163.05  5832.5 2163.73
#Mann= 3 ,-1 , 0
  4462.8     .07       0  5253.2     .05       0  5259.2     .07       0
Bank Sta=5253.2,5259.2
XS Rating Curve= 0 ,0
Exp/Cntr=0.3,0.1

Type RM Length L Ch R = 1 ,60025   ,422,422,422
BEGIN DESCRIPTION:
Bear Creek 2 110.0
END DESCRIPTION:
XS GIS Cut Line= 3
        1803375.       13961175.        1802975.       13960875.
      1802175.01     13960175.01
#Sta/Elev= 30
  4495.1 2155.67    4667 2149.93    4767 2148.09  4845.1 2143.81  4908.6 2142.57
  4958.6 2142.77    4992 2139.93  5002.2 2139.89  5023.1 2142.33  5051.6 2143.68
    5137 2143.14  5186.3 2140.92  5232.7 2136.99  5233.2 2136.49  5238.7 2136.99
  5257.5 2138.44  5264.2 2140.28  5278.4 2141.73  5327.8 2145.56  5370.5  2145.9
  5427.4 2149.98  5484.4 2152.54    5640 2156.01  5682.7 2160.15  5725.4 2162.18
  5795.7 2163.29  5852.6 2165.84  5951.8 2168.14  6001.6 2172.72  6058.1  2176.5
#Mann= 3 ,-1 , 0
  4495.1     .07       0  5232.7     .05       0  5238.7     .07       0
Bank Sta=5232.7,5238.7
XS Rating Curve= 0 ,0
Exp/Cntr=0.3,0.1

Type RM Length L Ch R = 1 ,59603   ,449,449,449
BEGIN DESCRIPTION:
Bear Creek 2 109.0
END DESCRIPTION:
XS GIS Cut Line= 3
      1803525.03     13960725.02        1803175.       13960525.
      1802475.05     13960275.02
#Sta/Elev= 30
  4592.8  2152.5    4731 2148.98  4805.2 2145.22    4821 2143.45  4848.4 2141.86
  4915.3 2140.09  4944.8 2137.87  4998.6  2137.4  5011.3 2136.06  5042.1 2138.25
  5059.7 2140.27  5080.9 2140.53  5091.5 2140.09  5103.7 2137.48  5131.5 2133.78
    5132 2133.28  5137.1 2133.28  5137.6 2133.78  5176.5 2134.71  5221.6  2138.8
  5261.4  2140.6  5277.9 2142.46  5303.4 2143.97  5370.3 2144.75  5431.8 2148.78
  5518.9 2151.82  5537.5 2153.07  5611.8 2154.82  5675.5 2159.29  5739.2 2161.62
#Mann= 3 ,-1 , 0
  4592.8     .07       0  5131.5     .05       0  5137.6     .07       0
Bank Sta=5131.5,5137.6
XS Rating Curve= 0 ,0
Exp/Cntr=0.3,0.1

Type RM Length L Ch R = 1 ,59154   ,466,466,466
BEGIN DESCRIPTION:
Bear Creek 2 108.0
END DESCRIPTION:
XS GIS Cut Line= 4
      1803500.12     13960400.12        1803425.       13960325.
        1803225.       13960125.      1802974.98       13960125.
#Sta/Elev= 30
    4616 2146.45  4736.4 2142.87  4750.5 2141.34  4764.7 2140.92    4793  2139.1
  4807.1 2138.46  4835.4 2137.86  4849.5 2136.57  4877.8  2135.7  4920.2 2132.79
  4934.4 2131.31  4972.2 2126.39  4972.7 2125.89    4981 2125.89  4981.5 2126.39
  4990.9 2127.97  5007.6 2128.33  5025.1 2130.58  5035.1 2130.42  5045.1 2132.07
  5055.1 2133.01  5065.1 2133.52  5075.1 2134.71  5095.1 2135.25  5115.1 2136.44
  5165.1 2137.81  5205.1  2140.3  5225.1 2141.05  5245.1 2141.39  5255.1 2142.01
#Mann= 3 ,-1 , 0
    4616     .07       0  4972.2     .05       0  4981.5     .07       0
Bank Sta=4972.2,4981.5
XS Rating Curve= 0 ,0
Exp/Cntr=0.3,0.1