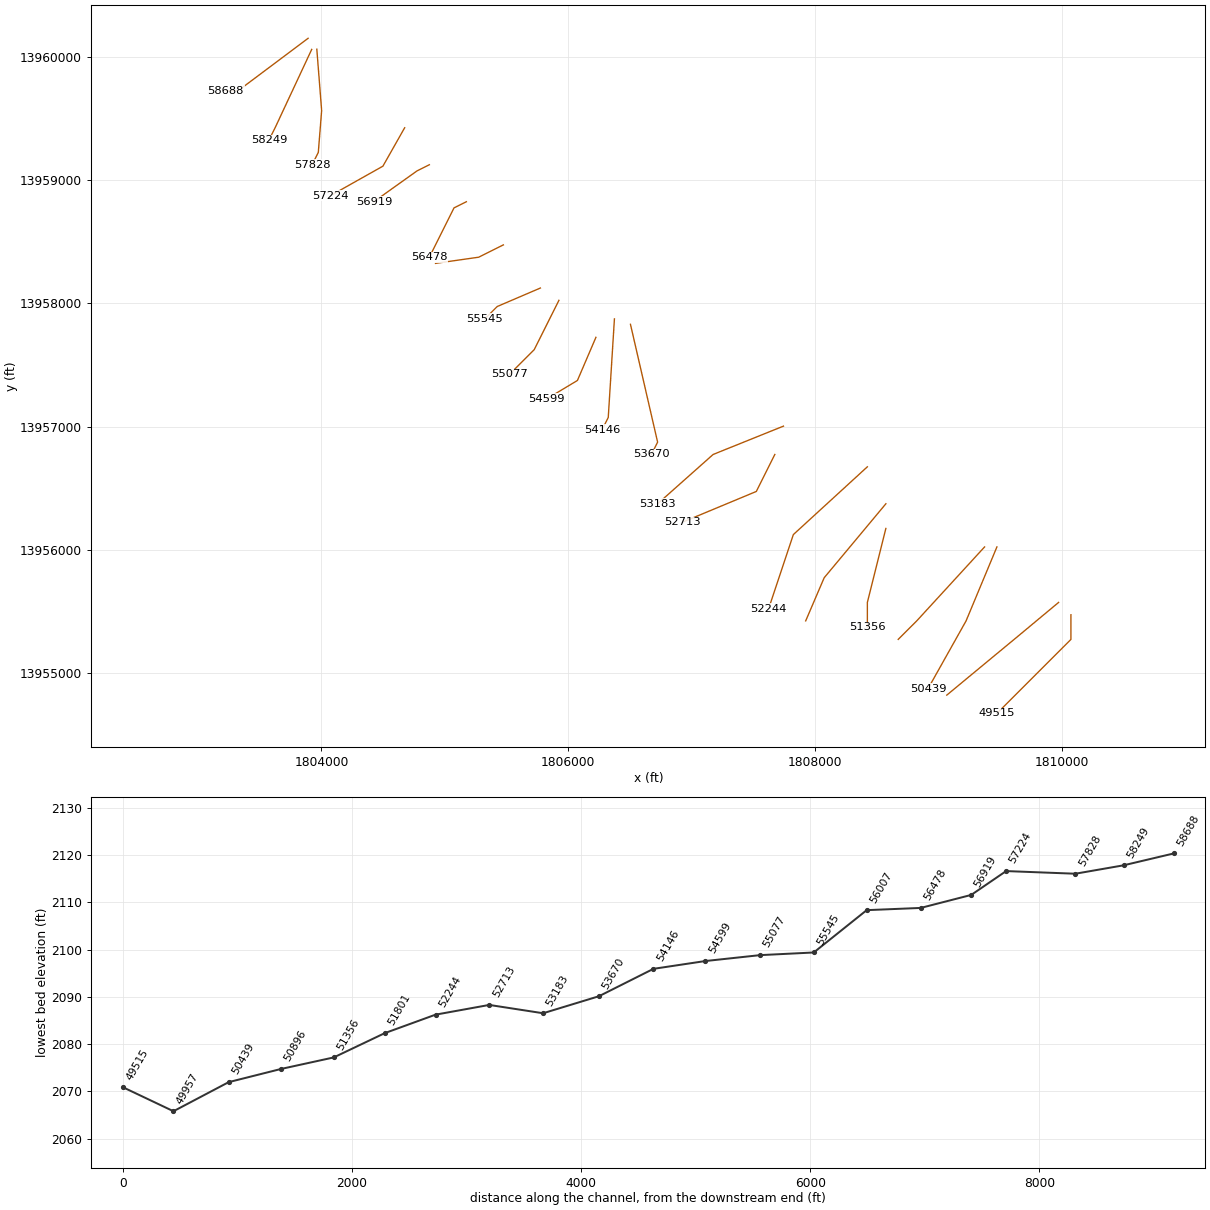
HEC-RAS study Bear Creek 2.prj: Bear Creek 2 Base Level Engineering

--- Bear Creek 2.g01 (geometry) --- (continued)

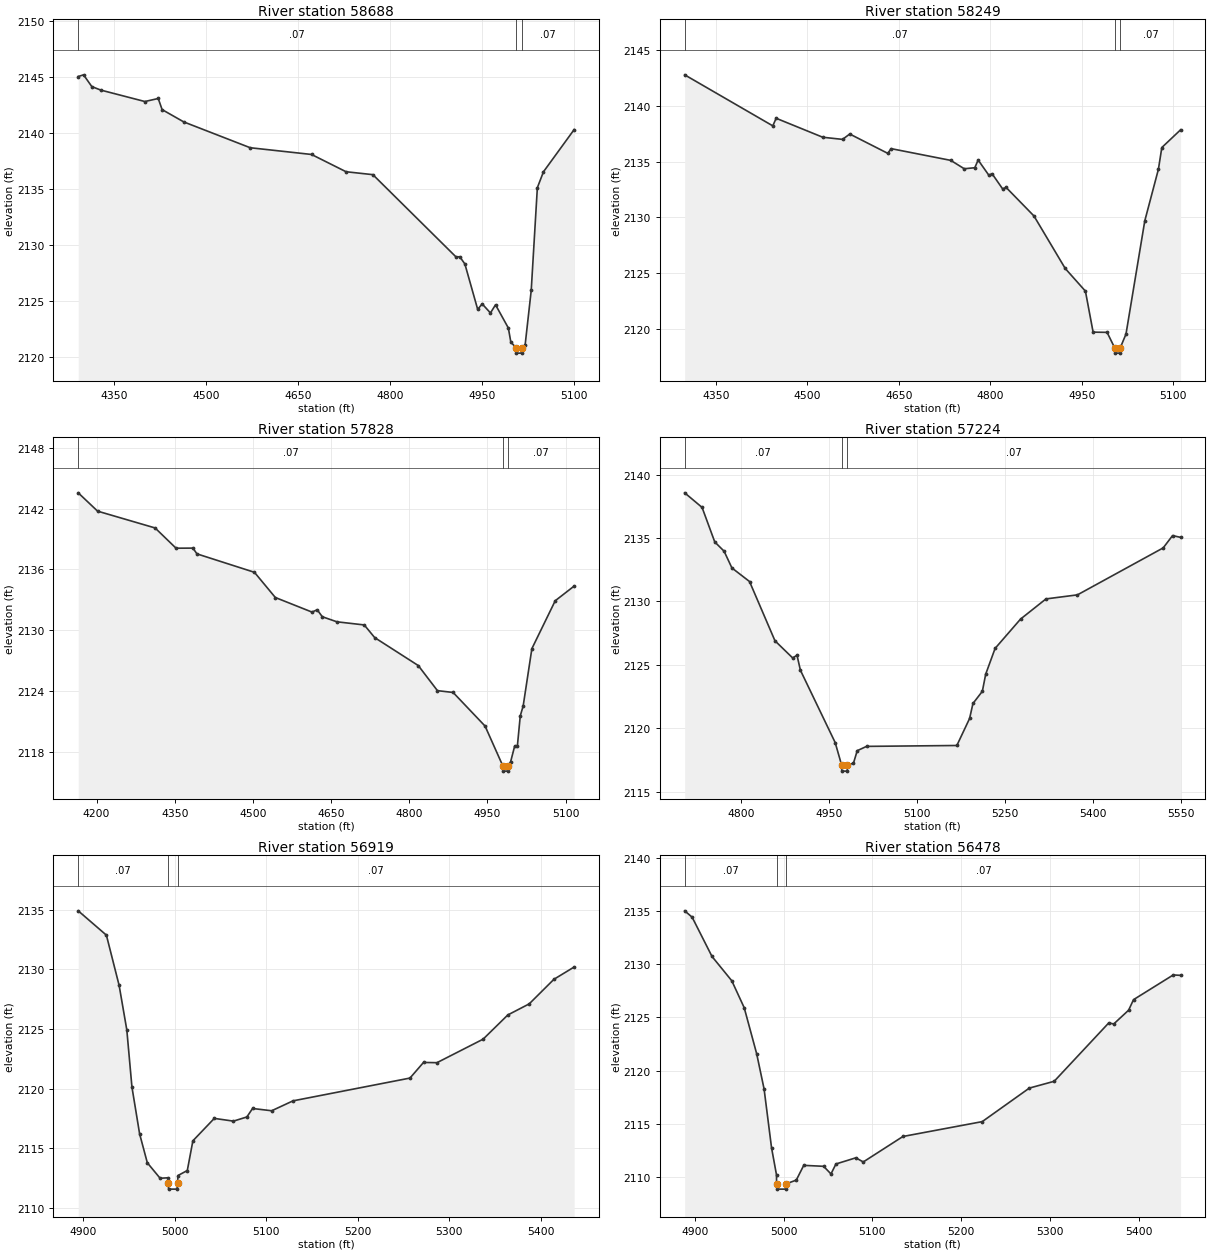
Type RM Length L Ch R = 1 ,58688   ,439,439,439
BEGIN DESCRIPTION:
Bear Creek 2 107.0
END DESCRIPTION:
XS GIS Cut Line= 4
      1803891.93      13960150.2        1803525.       13959875.
        1803325.       13959725.      1803224.97       13959725.
#Sta/Elev= 30
  4291.3 2145.03    4300 2145.18  4313.5 2144.13  4328.1 2143.82    4400  2142.8
  4421.8 2143.07  4428.1 2142.08  4463.5 2140.98  4571.8 2138.68  4671.8 2138.08
  4728.1 2136.54  4771.8 2136.28  4907.3 2128.95  4913.5 2128.96  4921.8 2128.32
  4942.7 2124.27    4950 2124.76  4963.5 2123.95  4971.8 2124.68  4992.7 2122.61
  4996.8 2121.34  5005.2 2120.87  5005.7 2120.37  5014.2 2120.37  5014.7 2120.87
    5020 2121.07    5030 2125.96    5040 2135.12    5050 2136.54    5100  2140.3
#Mann= 3 ,-1 , 0
  4291.3     .07       0  5005.2     .05       0  5014.7     .07       0
Bank Sta=5005.2,5014.7
XS Rating Curve= 0 ,0
Exp/Cntr=0.3,0.1

Type RM Length L Ch R = 1 ,58249   ,421,421,421
BEGIN DESCRIPTION:
Bear Creek 2 106.0
END DESCRIPTION:
XS GIS Cut Line= 3
      1803921.38     13960060.11        1803625.       13959425.
      1803574.98     13959324.97
#Sta/Elev= 30
  4299.1 2142.77  4443.5  2138.2    4449 2138.88  4525.4 2137.18  4557.8 2136.99
  4569.6 2137.47  4631.9 2135.74  4637.4 2136.16  4735.1 2135.11  4757.2 2134.36
  4774.5 2134.45    4780 2135.14  4797.4 2133.79  4802.9 2133.91  4820.2 2132.55
  4825.8 2132.69  4871.5 2130.13  4922.7 2125.43  4955.8  2123.4  4968.4 2119.73
  4991.3 2119.71  5003.5 2118.35    5004 2117.85  5012.6 2117.85  5013.1 2118.35
  5022.3 2119.56  5053.1  2129.7  5075.4 2134.31    5081 2136.26  5111.8 2137.85
#Mann= 3 ,-1 , 0
  4299.1     .07       0  5003.5     .05       0  5013.1     .07       0
Bank Sta=5003.5,5013.1
XS Rating Curve= 0 ,0
Exp/Cntr=0.3,0.1

Type RM Length L Ch R = 1 ,57828   ,604,604,604
BEGIN DESCRIPTION:
Bear Creek 2 105.0
END DESCRIPTION:
XS GIS Cut Line= 4
      1803962.99     13960062.09      1804002.02      13959564.6
        1803975.       13959225.        1803925.     13959124.99
#Sta/Elev= 30
  4164.8 2143.56    4202 2141.75  4312.3 2140.09  4352.5 2138.09  4384.9  2138.1
  4392.6 2137.53  4502.9 2135.71    4543 2133.22  4613.3 2131.78  4623.3 2132.01
  4633.1 2131.32  4661.1 2130.82  4713.6 2130.51  4733.6 2129.26  4817.2  2126.5
    4854 2124.02  4884.1 2123.84  4945.4 2120.52  4979.6 2116.57  4980.1 2116.07
  4988.7 2116.07  4989.2 2116.57  4994.5 2117.01    5002 2118.51  5007.3 2118.51
  5012.9 2121.52  5018.5 2122.51  5035.2 2128.17    5080  2132.9  5116.3 2134.35
#Mann= 3 ,-1 , 0
  4164.8     .07       0  4979.6     .05       0  4989.2     .07       0
Bank Sta=4979.6,4989.2
XS Rating Curve= 0 ,0
Exp/Cntr=0.3,0.1

Type RM Length L Ch R = 1 ,57224   ,305,305,305
BEGIN DESCRIPTION:
Bear Creek 2 104.0
END DESCRIPTION:
XS GIS Cut Line= 3
        1804675.       13959425.      1804498.61     13959113.32
      1804074.98     13958874.99
#Sta/Elev= 30
  4704.6 2138.56  4734.2 2137.41  4755.8 2134.69  4771.7 2133.96    4785 2132.64
    4815 2131.57  4858.3  2126.9  4888.4 2125.55  4895.8 2125.76  4901.6 2124.58
  4960.8 2118.88  4971.6 2117.13  4972.1 2116.63  4981.2 2116.63  4981.7 2117.13
  4991.9 2117.25  4998.3 2118.24  5014.2 2118.58  5167.9 2118.65  5189.6 2120.78
  5195.3 2121.96  5211.3 2122.92    5217 2124.27    5233  2126.3  5276.3 2128.61
  5319.6  2130.2  5373.2 2130.52  5519.1 2134.22  5535.1 2135.19  5548.8 2135.05
#Mann= 3 ,-1 , 0
  4704.6     .07       0  4971.6     .05       0  4981.7     .07       0
Bank Sta=4971.6,4981.7
XS Rating Curve= 0 ,0
Exp/Cntr=0.3,0.1

Type RM Length L Ch R = 1 ,56919   ,441,441,441
BEGIN DESCRIPTION:
Bear Creek 2 103.0
END DESCRIPTION:
XS GIS Cut Line= 3
      1804875.02     13959125.01        1804775.       13959075.
      1804425.03     13958825.02
#Sta/Elev= 30
  4894.6 2134.91  4925.4 2132.87  4939.3 2128.66  4947.7 2124.93  4953.3 2120.14
  4961.7 2116.21  4970.1 2113.79  4984.1 2112.49  4992.4 2112.53  4992.9 2112.08
  4993.4 2111.58  5002.6 2111.58  5003.1 2112.08  5003.6 2112.72  5013.8 2113.14
  5019.9 2115.63  5043.3 2117.51  5064.2 2117.28  5078.9 2117.63  5085.1 2118.34
    5106 2118.15  5129.3 2118.98  5257.1 2120.89  5271.9  2122.2  5286.6 2122.18
    5337 2124.15    5364 2126.18  5387.4 2127.11  5414.4 2129.17  5436.5  2130.2
#Mann= 3 ,-1 , 0
  4894.6     .07       0  4992.9     .05       0  5003.1     .07       0
Bank Sta=4992.9,5003.1
XS Rating Curve= 0 ,0
Exp/Cntr=0.3,0.1

Type RM Length L Ch R = 1 ,56478   ,471,471,471
BEGIN DESCRIPTION:
Bear Creek 2 102.0
END DESCRIPTION:
XS GIS Cut Line= 3
      1805175.03     13958825.01        1805075.       13958775.
      1804875.02     13958375.04
#Sta/Elev= 30
  4888.4 2135.05  4896.8 2134.45  4919.2 2130.75  4941.5 2128.46  4955.5 2125.92
  4969.5  2121.6  4977.9 2118.27  4986.3 2112.73  4991.9 2110.17    4992 2109.33
  4992.5 2108.83  5002.3 2108.83  5002.8 2109.33  5014.2 2109.68  5022.6 2111.07
    5045 2110.98  5053.3 2110.26  5058.9  2111.2  5081.3 2111.78  5089.7 2111.39
  5134.4 2113.79  5223.8 2115.19  5276.9 2118.35  5304.9 2118.99  5366.4 2124.49
    5372 2124.39  5388.8 2125.69  5394.3 2126.68  5439.1 2129.01  5447.4 2128.97
#Mann= 3 ,-1 , 0
  4888.4     .07       0    4992     .05       0  5002.8     .07       0
Bank Sta=4992,5002.8
XS Rating Curve= 0 ,0
Exp/Cntr=0.3,0.1

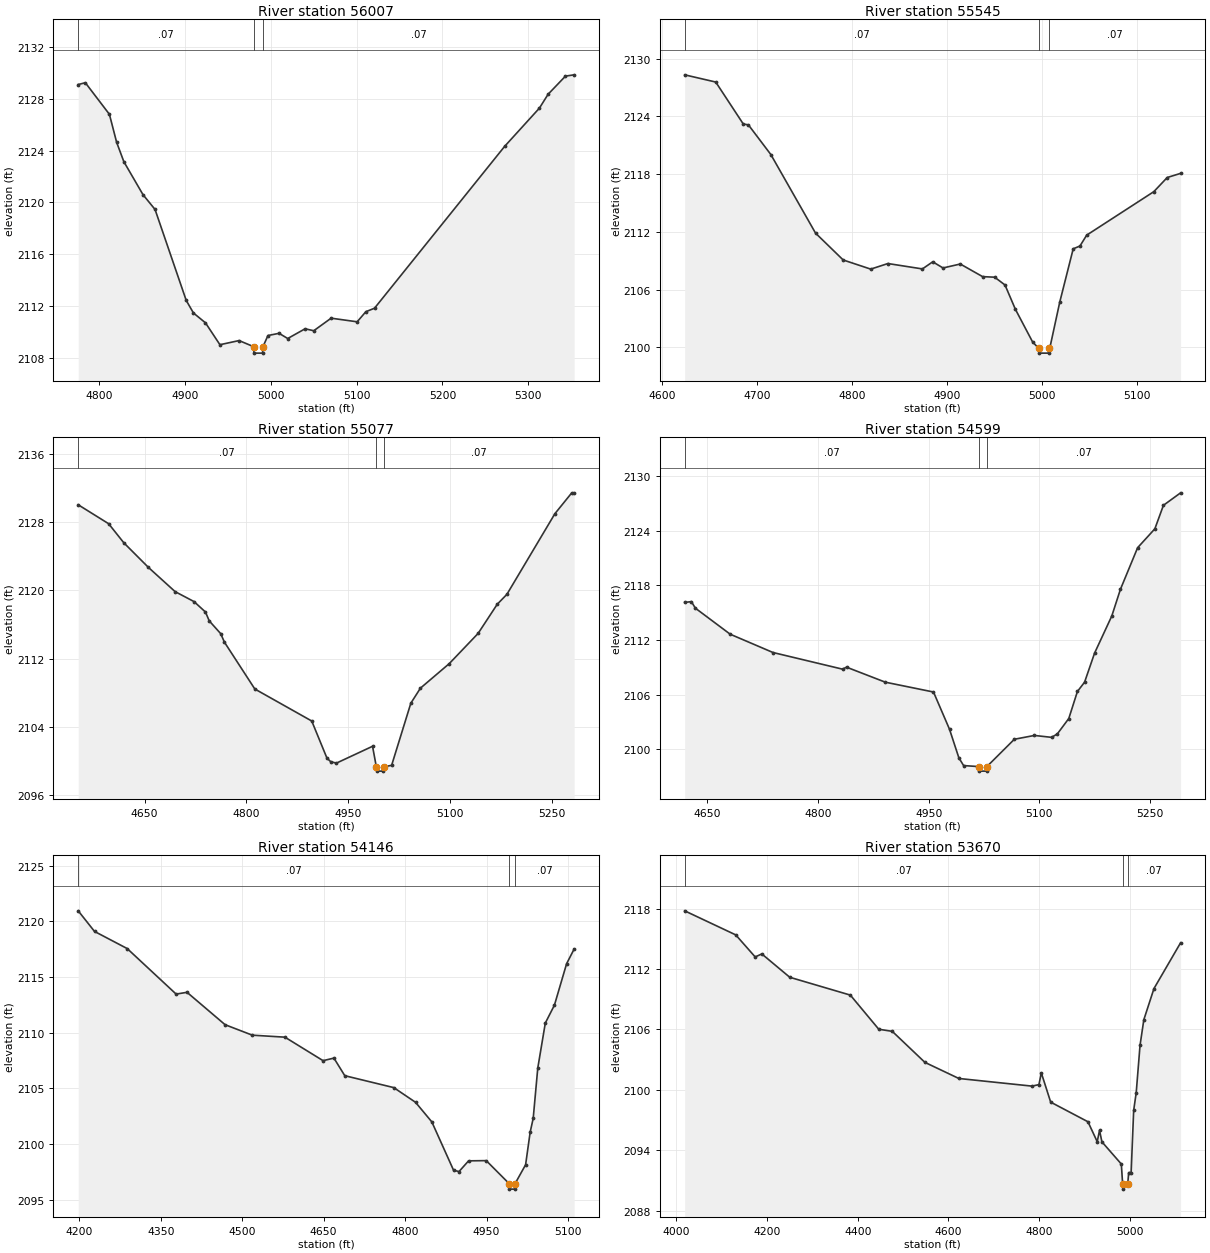
Type RM Length L Ch R = 1 ,56007   ,462,462,462
BEGIN DESCRIPTION:
Bear Creek 2 101.0
END DESCRIPTION:
XS GIS Cut Line= 3
      1805474.97     13958474.98        1805275.       13958375.
      1804925.02       13958325.
#Sta/Elev= 30
  4776.1 2129.11  4784.4 2129.25  4812.4 2126.81  4820.8 2124.65  4829.2 2123.15
  4851.5  2120.6  4865.5 2119.46  4901.8 2112.43  4910.2 2111.46  4924.2  2110.7
    4941 2109.01  4963.3 2109.33  4980.2 2108.86  4980.7 2108.36  4990.6 2108.36
  4991.1 2108.86  4996.9 2109.72  5009.8 2109.89  5019.9 2109.49  5040.1 2110.24
  5050.2 2110.09  5070.4 2111.06  5100.7 2110.78  5110.8 2111.56  5120.9 2111.83
  5272.4 2124.34  5312.8 2127.29  5322.9 2128.36  5343.1 2129.76  5353.2 2129.86
#Mann= 3 ,-1 , 0
  4776.1     .07       0  4980.2     .05       0  4991.1     .07       0
Bank Sta=4980.2,4991.1
XS Rating Curve= 0 ,0
Exp/Cntr=0.3,0.1

Type RM Length L Ch R = 1 ,55545   ,468,468,468
BEGIN DESCRIPTION:
Bear Creek 2 100.0
END DESCRIPTION:
XS GIS Cut Line= 3
      1805775.03     13958125.01        1805425.       13957975.
      1805325.03     13957875.03
#Sta/Elev= 30
  4623.7 2128.32  4656.4 2127.57  4685.4 2123.21  4690.8 2123.12  4714.4 2120.04
  4761.5 2111.87  4790.6 2109.08  4819.6 2108.13  4837.7 2108.71    4874 2108.15
  4884.9 2108.89  4895.7 2108.25  4913.9 2108.66  4937.4 2107.35  4950.1 2107.29
    4961 2106.48  4971.9 2103.96    4990 2100.57  4996.4  2099.9  4996.9  2099.4
  5006.8  2099.4  5007.3  2099.9  5008.1  2099.9  5018.7 2104.73  5032.8 2110.24
  5039.9 2110.53    5047 2111.66  5117.7 2116.18  5131.8 2117.65  5145.9 2118.08
#Mann= 3 ,-1 , 0
  4623.7     .07       0  4996.4     .05       0  5007.3     .07       0
Bank Sta=4996.4,5007.3
XS Rating Curve= 0 ,0
Exp/Cntr=0.3,0.1

Type RM Length L Ch R = 1 ,55077   ,478,478,478
BEGIN DESCRIPTION:
Bear Creek 2 99.0
END DESCRIPTION:
XS GIS Cut Line= 3
      1805925.01     13958025.03        1805725.       13957625.
      1805524.99     13957424.99
#Sta/Elev= 30
  4552.4 2130.04  4597.2 2127.82  4619.5 2125.59  4655.8  2122.7    4695 2119.87
  4722.9  2118.7  4739.7 2117.48  4745.3 2116.44  4762.1 2114.95  4767.7 2113.94
  4812.4 2108.46  4896.2 2104.71  4918.6 2100.36  4924.2 2099.94  4932.6 2099.78
  4985.7 2101.75  4991.3 2099.34  4991.8 2098.84  5001.8 2098.84  5002.3 2099.34
  5013.8 2099.52  5042.1  2106.8  5056.2 2108.56  5098.6 2111.43  5141.1 2114.97
  5169.3 2118.39  5183.5 2119.55  5254.2    2129    5279 2131.44  5282.5 2131.44
#Mann= 3 ,-1 , 0
  4552.4     .07       0  4991.3     .05       0  5002.3     .07       0
Bank Sta=4991.3,5002.3
XS Rating Curve= 0 ,0
Exp/Cntr=0.3,0.1

Type RM Length L Ch R = 1 ,54599   ,453,453,453
BEGIN DESCRIPTION:
Bear Creek 2 98.0
END DESCRIPTION:
XS GIS Cut Line= 3
        1806225.       13957725.        1806075.       13957375.
      1805825.03     13957225.02
#Sta/Elev= 30
  4619.2 2116.12  4628.3 2116.21  4633.7 2115.49  4680.9 2112.63  4738.9 2110.62
  4833.2 2108.79  4838.6 2109.01  4891.2 2107.36  4956.5 2106.28  4978.2 2102.19
  4990.9 2099.05  4997.3  2098.2  5017.8 2098.09  5018.3 2097.59  5028.4 2097.59
  5028.9 2098.09  5066.1 2101.09  5093.3 2101.51  5116.6  2101.3  5124.4 2101.68
  5139.9 2103.37  5151.6 2106.34  5161.3 2107.36  5174.9 2110.56  5198.2 2114.63
  5209.9 2117.56  5233.2 2122.13  5256.6 2124.21  5268.2 2126.79  5291.5 2128.16
#Mann= 3 ,-1 , 0
  4619.2     .07       0  5017.8     .05       0  5028.9     .07       0
Bank Sta=5017.8,5028.9
XS Rating Curve= 0 ,0
Exp/Cntr=0.3,0.1

Type RM Length L Ch R = 1 ,54146   ,476,476,476
BEGIN DESCRIPTION:
Bear Creek 2 97.0
END DESCRIPTION:
XS GIS Cut Line= 3
        1806375.     13957874.97        1806325.       13957075.
      1806275.02     13956975.03
#Sta/Elev= 30
  4198.1 2120.94  4228.1 2119.09  4288.3 2117.55  4378.4 2113.46  4398.5 2113.62
  4468.6 2110.71  4518.7 2109.77  4578.8 2109.59    4649 2107.48    4669 2107.71
    4689 2106.13  4779.2 2105.06  4819.3 2103.74  4849.3 2101.98  4889.4 2097.63
  4899.4 2097.52    4917 2098.48  4949.5  2098.5  4991.6 2096.44  4992.1 2095.94
  5002.2 2095.94  5002.7 2096.44    5022 2098.13  5030.4 2101.06    5036  2102.3
  5044.4 2106.81  5058.3 2110.86  5075.1 2112.47  5097.5 2116.19  5111.4 2117.51
#Mann= 3 ,-1 , 0
  4198.1     .07       0  4991.6     .05       0  5002.7     .07       0
Bank Sta=4991.6,5002.7
XS Rating Curve= 0 ,0
Exp/Cntr=0.3,0.1

Type RM Length L Ch R = 1 ,53670   ,487,487,487
BEGIN DESCRIPTION:
Bear Creek 2 96.0
END DESCRIPTION:
XS GIS Cut Line= 3
      1806504.99     13957830.61        1806725.       13956875.
      1806675.01     13956775.01
#Sta/Elev= 30
  4018.9 2117.78  4131.4 2115.39  4174.2  2113.2  4188.8  2113.5  4250.4 2111.18
  4383.8 2109.41  4446.4 2106.02  4476.2 2105.81    4548 2102.73  4622.8 2101.13
    4784 2100.37  4799.2 2100.52  4804.5 2101.68  4825.1 2098.78  4907.2 2096.83
  4927.6 2094.85  4932.7 2095.98  4937.9 2094.84  4980.7 2092.63  4983.6 2090.64
  4984.1 2090.14  4994.8 2090.64  4996.9 2091.78  5002.3 2091.78  5007.9 2097.96
  5013.5 2099.72  5021.9 2104.42  5030.3 2106.97  5052.6 2110.06  5111.3 2114.61
#Mann= 3 ,-1 , 0
  4018.9     .07       0  4983.6     .05       0  4994.8     .07       0
Bank Sta=4983.6,4994.8
XS Rating Curve= 0 ,0
Exp/Cntr=0.3,0.1

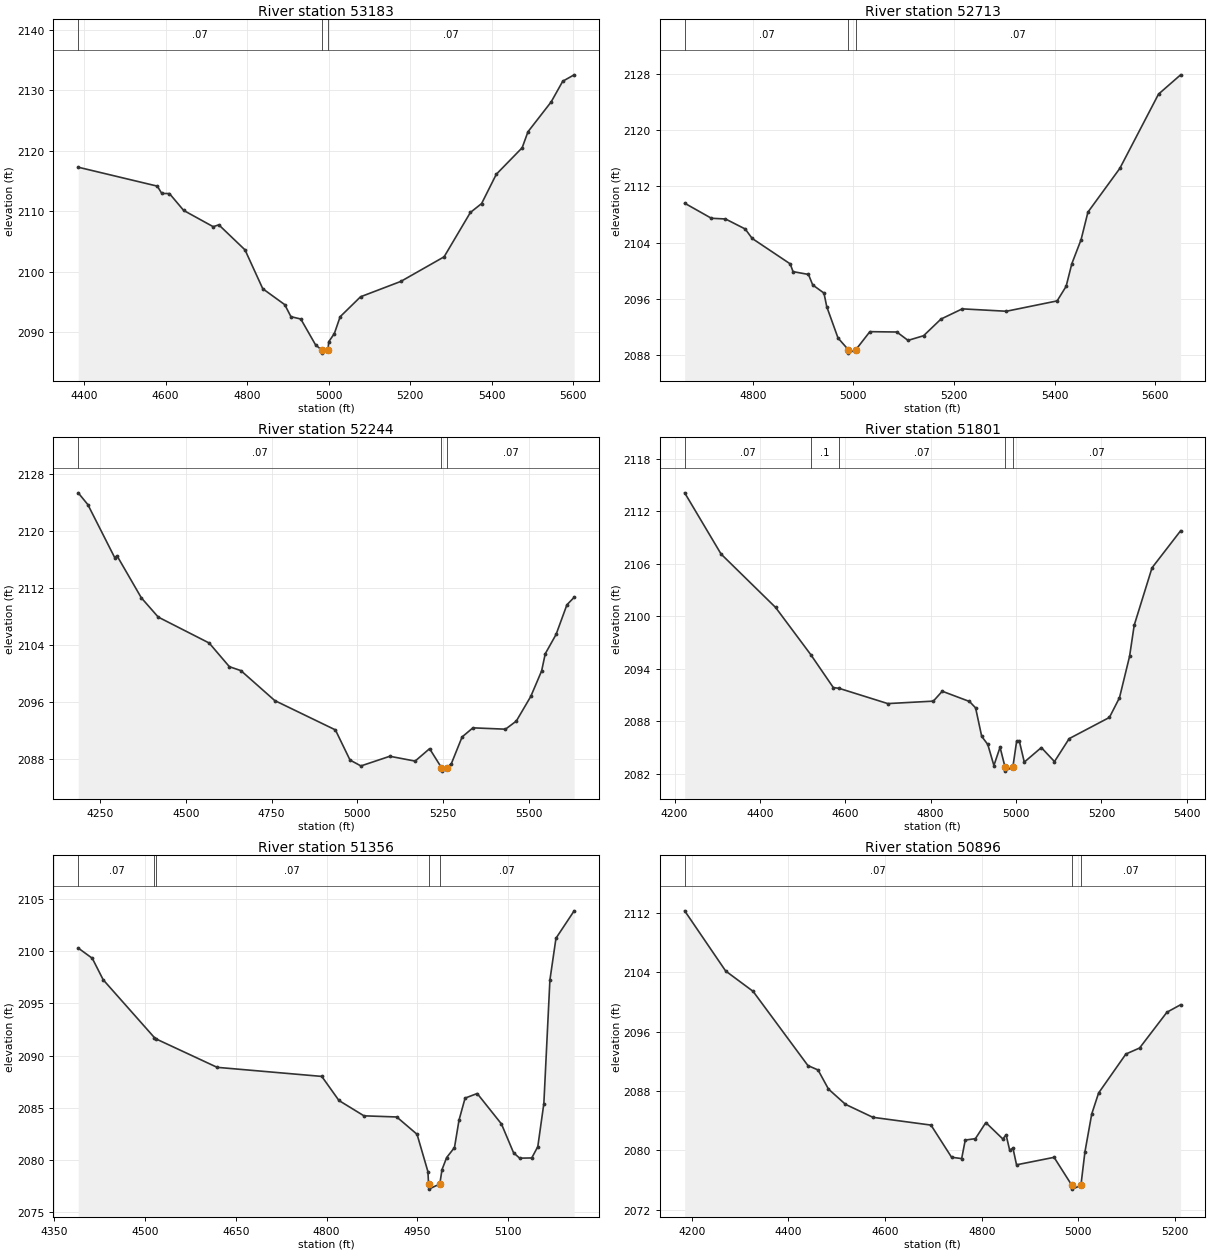
Type RM Length L Ch R = 1 ,53183   ,470,470,470
BEGIN DESCRIPTION:
Bear Creek 2 95.0
END DESCRIPTION:
XS GIS Cut Line= 3
      1807744.88     13957004.78        1807175.       13956775.
      1806725.03     13956375.03
#Sta/Elev= 30
  4385.5 2117.29  4579.5 2114.16  4590.5 2112.95  4609.3 2112.93  4644.2 2110.14
  4716.7 2107.45  4730.4 2107.76  4794.6 2103.62  4838.2 2097.19  4892.1 2094.56
  4907.3 2092.57  4931.5 2092.18  4967.6 2087.92  4982.9 2087.04  4983.4 2086.54
  4998.2 2087.04    5000 2088.42  5013.8 2089.78    5028 2092.56  5078.1 2095.86
  5176.8  2098.4    5283 2102.47  5347.4  2109.8    5375 2111.28    5411 2116.12
  5474.5 2120.51  5488.7 2123.15  5545.6 2128.09    5574 2131.51    5602 2132.57
#Mann= 3 ,-1 , 0
  4385.5     .07       0  4982.9     .05       0  4998.2     .07       0
Bank Sta=4982.9,4998.2
XS Rating Curve= 0 ,0
Exp/Cntr=0.3,0.1

Type RM Length L Ch R = 1 ,52713   ,469,469,469
BEGIN DESCRIPTION:
Bear Creek 2 94.0
END DESCRIPTION:
XS GIS Cut Line= 3
      1807675.02     13956775.04        1807525.       13956475.
      1806924.96     13956224.98
#Sta/Elev= 30
  4664.8  2109.6  4717.9 2107.46  4745.9 2107.36    4785 2105.94    4799 2104.59
  4874.5 2100.98  4880.1 2099.88  4910.8 2099.48  4919.2 2097.99  4941.6 2096.83
  4947.1  2094.9  4969.5 2090.45  4989.8  2088.8  4990.3  2088.3  5005.1  2088.8
  5032.8 2091.35  5086.4  2091.3  5108.6 2090.11  5139.5 2090.77  5174.1 2093.14
  5216.4 2094.59  5304.1 2094.25  5404.9 2095.72  5422.8 2097.79  5434.1    2101
  5452.5 2104.42  5466.1 2108.33  5529.5 2114.55  5606.4  2125.1  5650.3 2127.84
#Mann= 3 ,-1 , 0
  4664.8     .07       0  4989.8     .05       0  5005.1     .07       0
Bank Sta=4989.8,5005.1
XS Rating Curve= 0 ,0
Exp/Cntr=0.3,0.1

Type RM Length L Ch R = 1 ,52244   ,443,443,443
BEGIN DESCRIPTION:
Bear Creek 2 93.0
END DESCRIPTION:
XS GIS Cut Line= 3
      1808424.99     13956674.99        1807825.       13956125.
        1807625.     13955524.99
#Sta/Elev= 30
  4186.1 2125.39  4214.1 2123.74  4292.5 2116.28  4299.2 2116.54  4370.2 2110.62
  4419.5 2107.91  4568.1 2104.26    4627 2100.93  4660.6 2100.38  4759.2 2096.17
  4936.2 2092.04  4978.8  2087.8  5010.6 2086.97  5094.9 2088.33  5168.7 2087.65
  5210.9  2089.4  5245.4 2086.74  5245.9 2086.24  5260.7 2086.74  5274.1 2087.26
  5305.7 2091.05  5337.3 2092.33  5432.2 2092.14  5463.8 2093.28    5506 2096.75
  5537.6 2100.33  5548.2 2102.75  5579.8 2105.47  5611.4 2109.64  5632.5 2110.69
#Mann= 3 ,-1 , 0
  4186.1     .07       0  5245.4     .05       0  5260.7     .07       0
Bank Sta=5245.4,5260.7
XS Rating Curve= 0 ,0
Exp/Cntr=0.3,0.1

Type RM Length L Ch R = 1 ,51801   ,445,445,445
BEGIN DESCRIPTION:
Bear Creek 2 92.0
END DESCRIPTION:
XS GIS Cut Line= 3
      1808575.02     13956375.03        1808075.       13955775.
      1807925.02     13955425.04
#Sta/Elev= 30
  4223.8  2114.1  4309.1 2107.11  4436.7 2101.02    4519 2095.64    4572 2091.87
  4585.7 2091.78  4699.6 2090.04  4806.3 2090.32  4827.2 2091.45    4891 2090.28
  4905.3 2089.55  4919.6  2086.3  4933.9 2085.37  4948.2 2082.97  4962.6 2085.06
  4974.1 2082.83  4974.6 2082.33  4992.7 2082.83  5001.6 2085.79  5007.6 2085.79
  5019.4 2083.36  5059.3 2085.02  5090.1 2083.42  5124.5 2086.04  5218.8 2088.46
  5242.4 2090.71    5266 2095.43  5276.9 2098.99  5318.6 2105.54  5385.6 2109.77
#Mann= 5 ,-1 , 0
  4223.8     .07       0    4519      .1       0  4585.7     .07       0
  4974.1     .05       0  4992.7     .07       0
Bank Sta=4974.1,4992.7
XS Rating Curve= 0 ,0
Exp/Cntr=0.3,0.1

Type RM Length L Ch R = 1 ,51356   ,460,460,460
BEGIN DESCRIPTION:
Bear Creek 2 91.0
END DESCRIPTION:
XS GIS Cut Line= 3
        1808575.     13956174.99        1808425.       13955575.
        1808425.     13955374.95
#Sta/Elev= 30
  4390.1 2100.31  4413.3 2099.33  4431.3 2097.27  4515.9 2091.72  4518.4  2091.6
  4619.4 2088.87  4792.1    2088  4820.4 2085.69  4861.7 2084.22  4915.8 2084.11
  4949.3 2082.45  4967.3 2078.86  4968.3 2077.69  4968.8 2077.19  4986.9 2077.69
  4990.5 2079.06  4998.2 2080.22  5011.1 2081.18  5018.6 2083.81  5028.6 2085.92
  5048.6 2086.36  5088.6 2083.44  5108.6 2080.68  5118.6 2080.16  5138.6 2080.18
  5148.6 2081.26  5158.6  2085.4  5168.6 2097.25  5178.6 2101.25  5208.6 2103.88
#Mann= 5 ,-1 , 0
  4390.1     .07       0  4515.9      .1       0  4518.4     .07       0
  4968.3     .05       0  4986.9     .07       0
Bank Sta=4968.3,4986.9
XS Rating Curve= 0 ,0
Exp/Cntr=0.3,0.1

Type RM Length L Ch R = 1 ,50896   ,457,457,457
BEGIN DESCRIPTION:
Bear Creek 2 90.0
END DESCRIPTION:
XS GIS Cut Line= 3
        1809375.       13956025.        1808825.       13955425.
      1808674.98     13955274.98
#Sta/Elev= 30
  4185.4  2112.3  4270.2 2104.18  4326.9 2101.44  4440.4 2091.42  4461.3 2090.83
  4482.9 2088.25  4518.1 2086.19  4574.8 2084.44    4695 2083.39  4737.6 2079.05
  4758.5 2078.87  4765.9 2081.37  4786.9 2081.56  4808.5 2083.73  4843.6 2081.52
  4850.4 2082.08  4857.8    2080  4864.6 2080.28    4872 2078.03  4949.7 2079.04
  4986.6 2075.25  4987.1 2074.75  5005.2 2075.25  5013.5 2079.76  5027.6 2084.89
  5041.8 2087.72  5098.3 2092.98  5126.6 2093.79  5183.2 2098.62  5211.5 2099.63
#Mann= 3 ,-1 , 0
  4185.4     .07       0  4986.6     .05       0  5005.2     .07       0
Bank Sta=4986.6,5005.2
XS Rating Curve= 0 ,0
Exp/Cntr=0.3,0.1

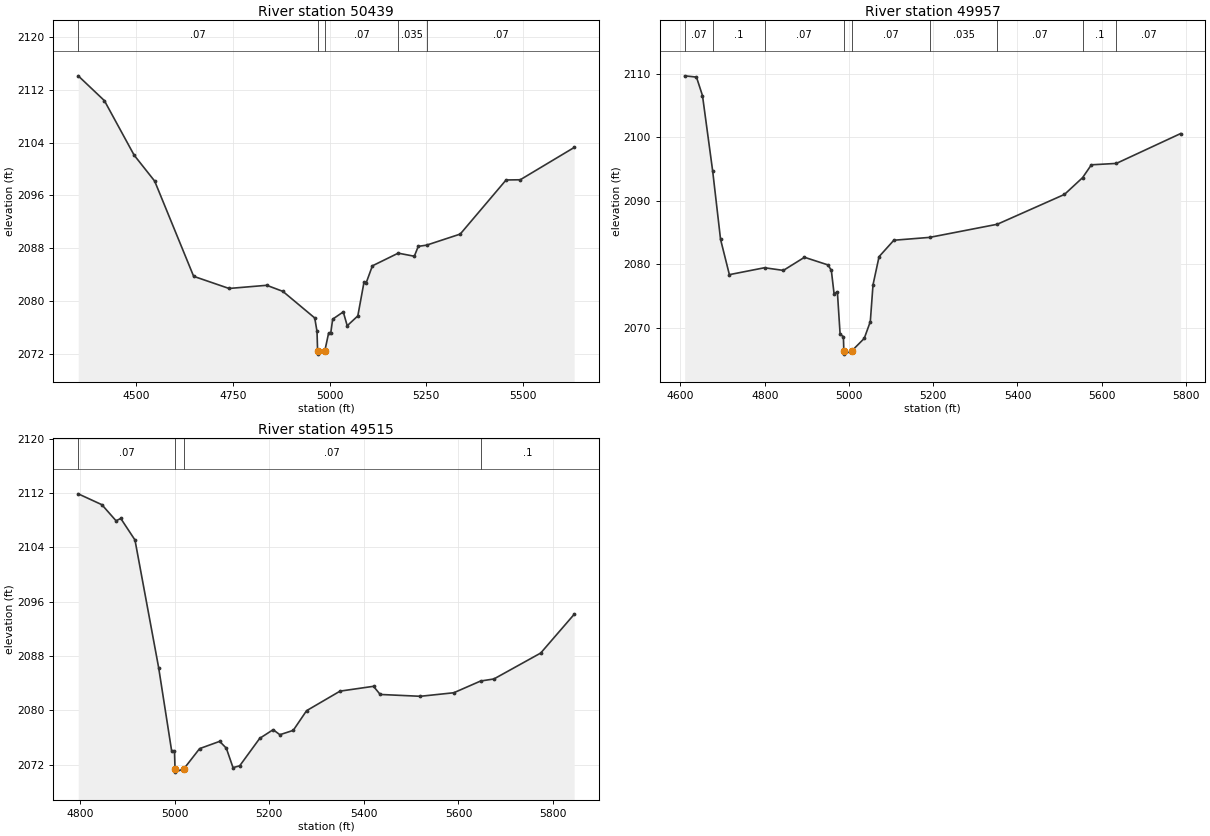
Type RM Length L Ch R = 1 ,50439   ,482,482,482
BEGIN DESCRIPTION:
Bear Creek 2 89.0
END DESCRIPTION:
XS GIS Cut Line= 3
      1809475.01     13956025.01        1809225.       13955425.
      1808915.63     13954873.46
#Sta/Elev= 30
  4349.9 2114.13  4417.6 2110.37  4494.5 2102.11  4547.6 2098.18  4648.4 2083.75
  4739.9 2081.91  4837.4 2082.39  4879.1 2081.47  4961.5 2077.44  4967.4 2075.39
  4968.9 2072.46  4969.4 2071.96  4987.6 2072.46  4997.2  2075.1  5002.8  2075.1
  5007.9 2077.26  5035.3 2078.36  5045.5 2076.26  5072.9 2077.75  5088.9 2082.86
  5094.6 2082.77  5110.6 2085.34  5177.4 2087.26    5219 2086.79  5229.2 2088.29
  5250.5 2088.47  5337.7 2090.15  5456.3 2098.35  5492.9 2098.38  5632.3 2103.27
#Mann= 5 ,-1 , 0
  4349.9     .07       0  4968.9     .05       0  4987.6     .07       0
  5177.4    .035       0  5250.5     .07       0
Bank Sta=4968.9,4987.6
XS Rating Curve= 0 ,0
Exp/Cntr=0.3,0.1

Type RM Length L Ch R = 1 ,49957   ,442,442,442
BEGIN DESCRIPTION:
Bear Creek 2 88.0
END DESCRIPTION:
XS GIS Cut Line= 3
      1809974.99     13955574.99        1809675.       13955325.
      1809068.82     13954823.23
#Sta/Elev= 30
    4610 2109.71    4638 2109.51  4652.3 2106.58  4676.5 2094.67  4695.2  2083.9
  4716.1 2078.34  4799.5 2079.43  4844.3 2079.01  4894.4 2081.08  4950.4 2079.87
  4958.2    2079  4964.7 2075.32  4972.5 2075.65    4979 2068.95  4986.8 2068.55
  4987.9  2066.3  4988.4  2065.8  5006.6  2066.3  5036.3 2068.28  5050.7 2070.93
  5057.1 2076.73  5071.5 2081.18  5106.6 2083.77  5191.6 2084.22  5352.1 2086.29
  5511.7    2091  5554.6 2093.64  5575.5 2095.67  5634.8 2095.89  5787.4  2100.6
#Mann= 9 ,-1 , 0
    4610     .07       0  4676.5      .1       0  4799.5     .07       0
  4987.9     .05       0  5006.6     .07       0  5191.6    .035       0
  5352.1     .07       0  5554.6      .1       0  5634.8     .07       0
Bank Sta=4987.9,5006.6
XS Rating Curve= 0 ,0
Exp/Cntr=0.3,0.1

Type RM Length L Ch R = 1 ,49515   ,580,580,580
BEGIN DESCRIPTION:
Bear Creek 2 87.0
END DESCRIPTION:
XS GIS Cut Line= 3
        1810075.       13955475.        1810075.       13955275.
      1809475.02     13954675.02
#Sta/Elev= 30
  4796.1 2111.88  4846.1 2110.28  4876.1 2107.91  4886.1 2108.25  4916.1 2105.08
  4966.1  2086.3  4993.6 2074.03  4999.6 2074.03  5000.8 2071.39  5001.3 2070.89
  5019.6 2071.39  5052.7 2074.35  5095.1 2075.42  5109.2 2074.42  5123.4 2071.55
  5137.5 2071.82  5179.9 2075.87  5208.2 2077.14  5222.4  2076.4  5250.7 2077.04
  5278.9 2079.94  5349.7 2082.82  5420.4 2083.53  5434.5 2082.33  5519.4 2082.06
  5590.1 2082.58  5646.9 2084.31  5674.9 2084.61  5773.9 2088.43  5844.6 2094.13
#Mann= 4 ,-1 , 0
  4796.1     .07       0  5000.8     .05       0  5019.6     .07       0
  5646.9      .1       0
Bank Sta=5000.8,5019.6
XS Rating Curve= 0 ,0
Exp/Cntr=0.3,0.1