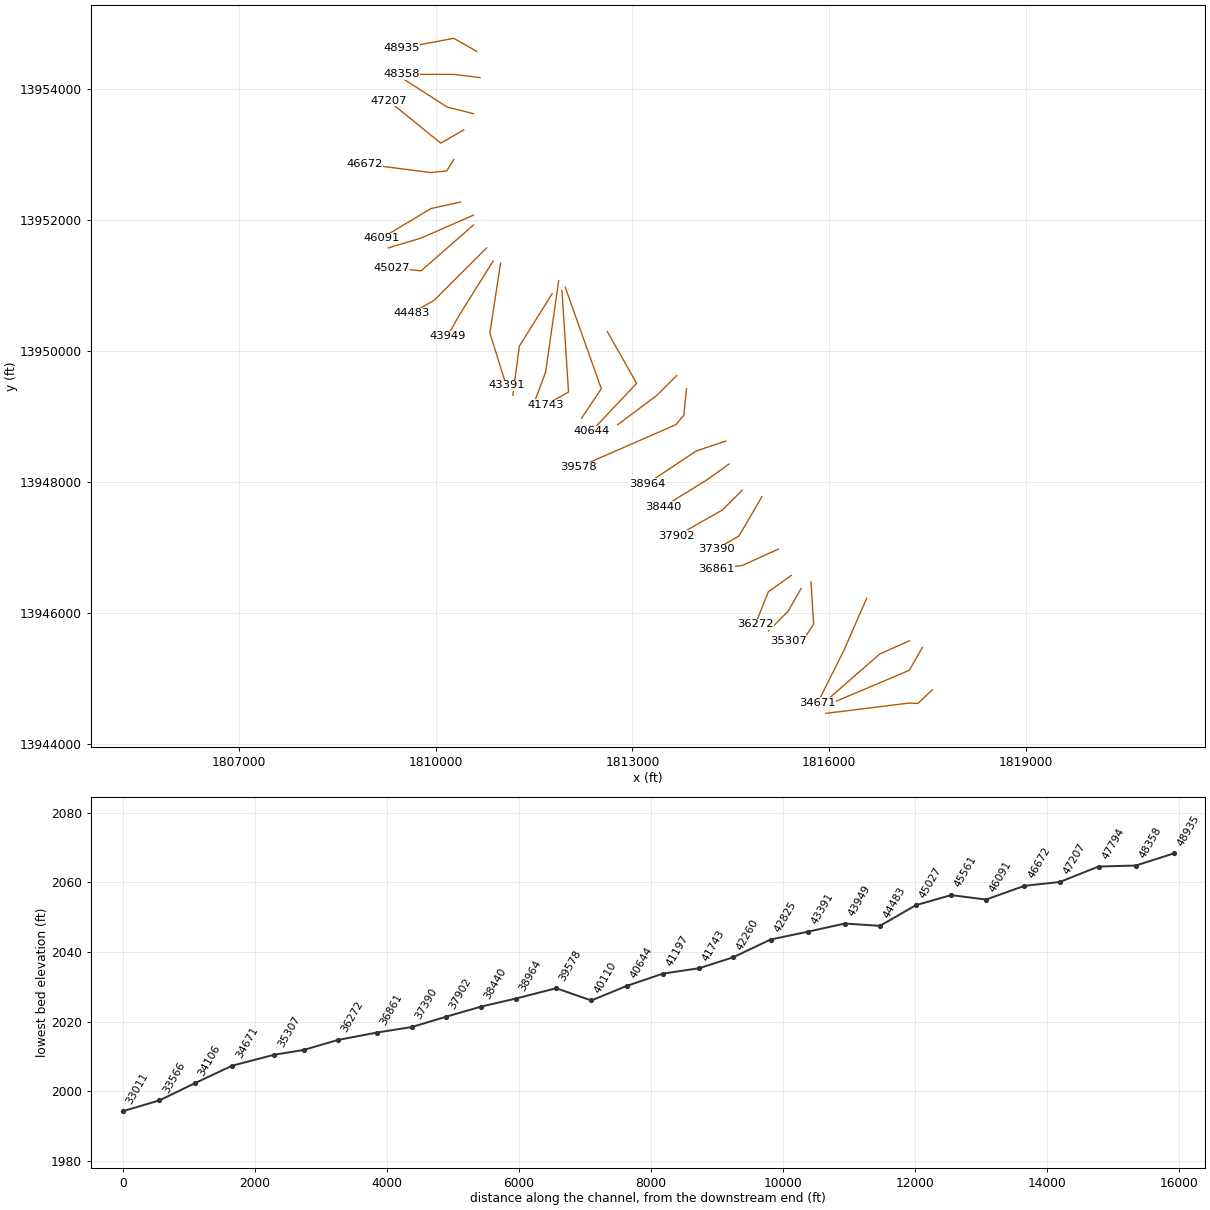
HEC-RAS study Bear Creek 2.prj: Bear Creek 2 Base Level Engineering

--- Bear Creek 2.g01 (geometry) --- (continued)

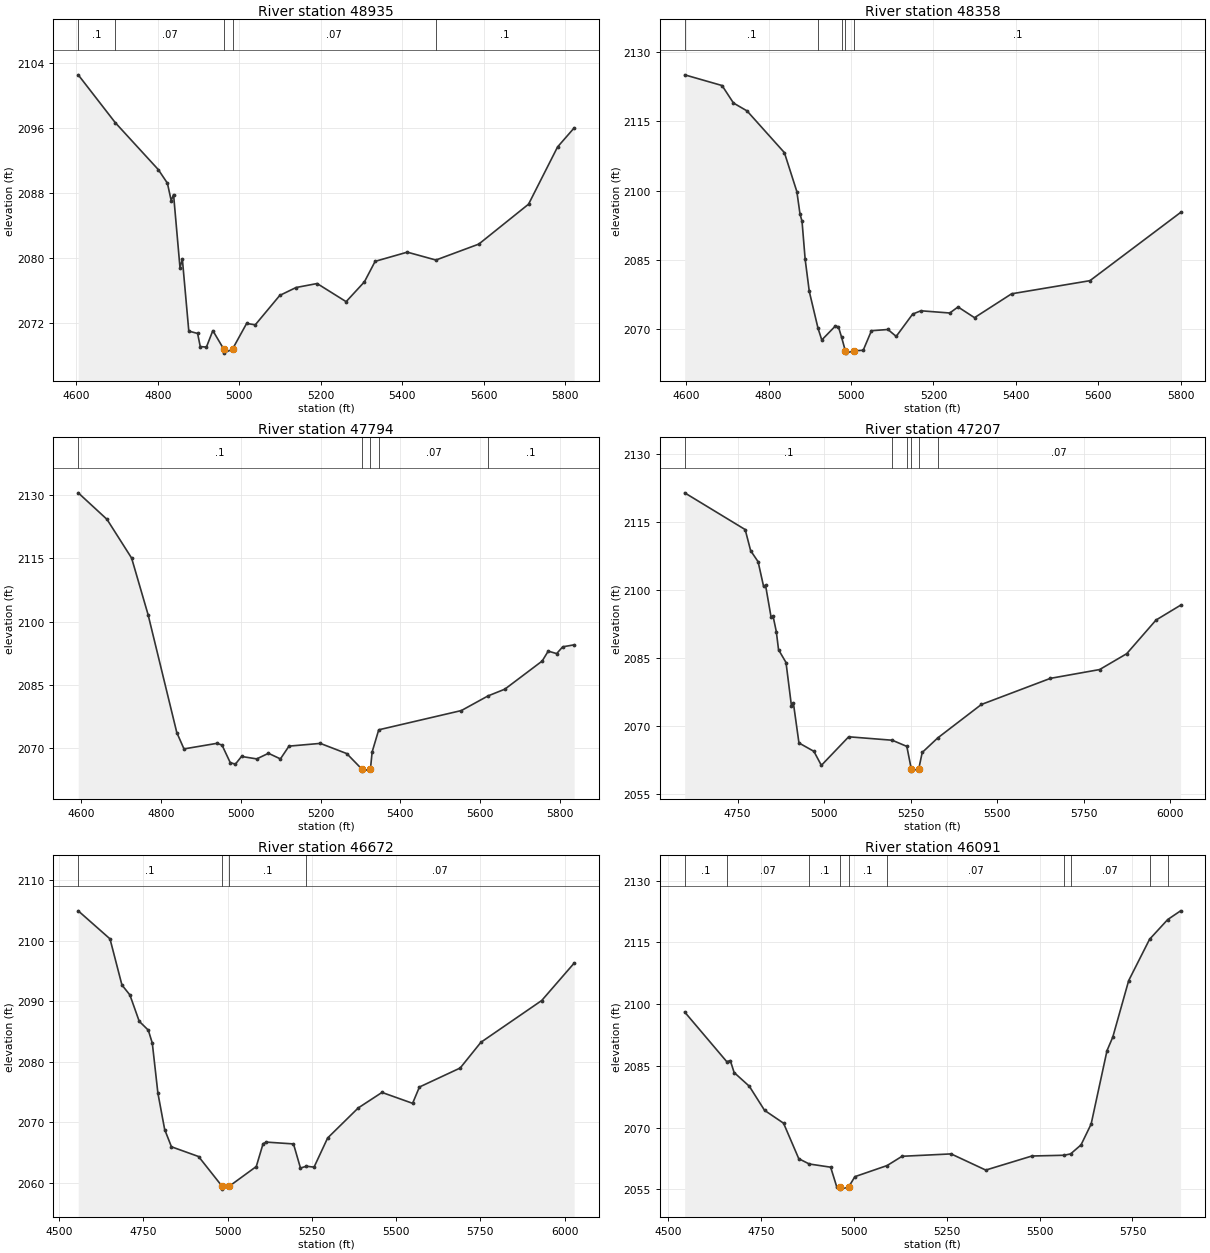
Type RM Length L Ch R = 1 ,48935   ,577,577,577
BEGIN DESCRIPTION:
Bear Creek 2 86.0
END DESCRIPTION:
XS GIS Cut Line= 3
      1810625.03     13954574.98        1810275.       13954775.
      1809474.99       13954625.
#Sta/Elev= 30
  4604.6 2102.53  4695.5 2096.65  4801.2 2090.87  4823.5  2089.2  4832.8 2087.06
  4838.6  2087.8  4854.4  2078.8  4860.2 2079.86    4876 2071.01  4897.6 2070.72
  4904.1 2069.11  4919.2 2069.04    4935 2071.07  4961.7  2068.8  4962.2  2068.3
  4983.3  2068.8  5017.9 2071.95  5039.1 2071.78  5099.3  2075.4  5139.2 2076.37
  5190.9 2076.86  5262.1 2074.63    5307 2077.07  5333.3 2079.59  5412.2 2080.72
  5482.4 2079.75  5587.7 2081.71  5709.8 2086.62    5781 2093.66  5821.7    2096
#Mann= 5 ,-1 , 0
  4604.6      .1       0  4695.5     .07       0  4961.7     .05       0
  4983.3     .07       0  5482.4      .1       0
Bank Sta=4961.7,4983.3
XS Rating Curve= 0 ,0
Exp/Cntr=0.3,0.1

Type RM Length L Ch R = 1 ,48358   ,564,564,564
BEGIN DESCRIPTION:
Bear Creek 2 85.0
END DESCRIPTION:
XS GIS Cut Line= 3
        1810675.       13954175.        1810275.       13954225.
      1809475.02       13954225.
#Sta/Elev= 30
  4596.5 2125.09  4687.2 2122.77  4714.9 2118.98  4747.7 2117.28  4838.4 2108.24
  4868.6 2099.81  4876.2    2095  4881.2 2093.35  4888.8 2085.11  4898.8 2078.17
    4920 2070.19  4929.1 2067.67  4961.8 2070.67  4969.4 2070.53  4977.3 2068.22
  4986.2 2065.32  4986.7 2064.82  5007.9 2065.32  5029.6 2065.44  5049.6 2069.67
  5089.6 2069.94  5109.6 2068.44  5149.6 2073.28  5169.6 2073.99  5239.6 2073.51
  5259.6 2074.82  5299.6  2072.5  5389.6 2077.67  5579.6 2080.51  5799.6 2095.29
#Mann= 5 ,-1 , 0
  4596.5      .1       0    4920     .07       0  4977.3      .1       0
  4986.2     .05       0  5007.9      .1       0
Bank Sta=4986.2,5007.9
XS Rating Curve= 0 ,0
Exp/Cntr=0.3,0.1

Type RM Length L Ch R = 1 ,47794   ,587,587,587
BEGIN DESCRIPTION:
Bear Creek 2 84.0
END DESCRIPTION:
XS GIS Cut Line= 3
      1810575.02     13953624.99        1810175.       13953725.
        1809475.       13954175.
#Sta/Elev= 30
  4591.9 2130.55  4664.1 2124.26  4725.9 2115.07  4767.2 2101.66  4839.3 2073.67
  4857.3  2069.8  4939.8 2071.12  4952.7 2070.72  4973.3 2066.57  4986.2 2066.17
  5001.7 2068.01  5039.9 2067.43  5069.3 2068.76  5099.3 2067.43  5120.8 2070.46
  5199.4 2071.11  5265.8 2068.69  5303.5 2065.03    5304 2064.53  5325.2 2065.03
  5329.5 2069.09    5346 2074.33  5553.4  2078.9  5620.2 2082.37  5662.4 2083.97
  5756.2 2090.65  5771.3    2093  5792.5 2092.41  5807.7 2094.02  5836.4 2094.49
#Mann= 5 ,-1 , 0
  4591.9      .1       0  5303.5     .05       0  5325.2      .1       0
    5346     .07       0  5620.2      .1       0
Bank Sta=5303.5,5325.2
XS Rating Curve= 0 ,0
Exp/Cntr=0.3,0.1

Type RM Length L Ch R = 1 ,47207   ,535,535,535
BEGIN DESCRIPTION:
Bear Creek 2 83.0
END DESCRIPTION:
XS GIS Cut Line= 3
      1810424.98     13953374.99        1810075.       13953175.
      1809274.97     13953825.02
#Sta/Elev= 30
  4596.8 2121.53  4771.7 2113.42  4787.5 2108.77  4809.1 2106.32    4825 2100.86
  4830.7 2101.08  4846.6  2094.1  4852.3 2094.33  4861.7 2090.92  4868.2  2086.9
  4889.8 2084.07  4905.6 2074.44  4911.3 2075.03  4927.2 2066.32  4970.4 2064.47
    4992 2061.37    5071 2067.68  5196.9 2066.92  5239.1 2065.56  5251.9  2060.6
  5252.4  2060.1  5273.6  2060.6  5283.6 2064.22  5328.3 2067.42  5454.6 2074.81
  5654.3 2080.58  5796.5 2082.52  5874.8 2086.02  5959.6 2093.45  6030.7 2096.73
#Mann= 6 ,-1 , 0
  4596.8      .1       0  5196.9     .07       0  5239.1      .1       0
  5251.9     .05       0  5273.6      .1       0  5328.3     .07       0
Bank Sta=5251.9,5273.6
XS Rating Curve= 0 ,0
Exp/Cntr=0.3,0.1

Type RM Length L Ch R = 1 ,46672   ,581,581,581
BEGIN DESCRIPTION:
Bear Creek 2 82.0
END DESCRIPTION:
XS GIS Cut Line= 4
        1810275.       13952925.       1810166.6      13952751.5
        1809925.       13952725.      1808909.63      13952855.9
#Sta/Elev= 30
  4556.9 2104.93  4651.2  2100.3  4686.6 2092.69  4710.2 2091.05  4737.9  2086.7
  4764.8 2085.24  4776.7  2083.1  4793.3 2074.85  4813.4 2068.84  4833.5 2065.99
    4914 2064.38  4983.4  2059.5  4983.9    2059  5005.6  2059.5  5085.2 2062.73
  5105.4  2066.5  5115.4 2066.76  5195.6 2066.46  5216.3 2062.48    5234 2062.78
  5256.6 2062.63  5296.9 2067.44  5387.7  2072.4  5458.2 2074.96    5549 2073.16
  5569.2 2075.85  5690.2 2078.99  5751.6 2083.23  5932.1 2090.13  6028.3  2096.3
#Mann= 4 ,-1 , 0
  4556.9      .1       0  4983.4     .05       0  5005.6      .1       0
    5234     .07       0
Bank Sta=4983.4,5005.6
XS Rating Curve= 0 ,0
Exp/Cntr=0.3,0.1

Type RM Length L Ch R = 1 ,46091   ,530,530,530
BEGIN DESCRIPTION:
Bear Creek 2 81.0
END DESCRIPTION:
XS GIS Cut Line= 3
      1810374.98       13952275.        1809925.       13952175.
        1809175.       13951725.
#Sta/Elev= 30
    4544  2098.1  4657.3 2086.04  4666.9  2086.3  4677.2 2083.39  4718.1 2080.06
  4759.1 2074.21  4810.3 2071.08  4851.3 2062.45  4879.5 2061.17  4937.1 2060.39
  4953.7 2055.57  4963.1 2055.56  4963.6 2055.06  4985.4 2055.56  5002.4 2058.09
  5089.2 2060.79  5129.4 2063.04  5261.5 2063.62  5354.8 2059.69  5479.2 2063.11
  5565.5 2063.29  5583.3 2063.62  5611.4 2065.81  5638.6 2070.87  5681.4 2088.73
  5696.9    2092  5739.7 2105.73    5796 2115.78  5844.8 2120.57  5879.6 2122.69
#Mann= 10 ,-1 , 0
    4544      .1       0  4657.3     .07       0  4879.5      .1       0
  4963.1     .05       0  4985.4      .1       0  5089.2     .07       0
  5565.5      .1       0  5583.3     .07       0    5796      .1       0
  5844.8     .07       0
Bank Sta=4963.1,4985.4
XS Rating Curve= 0 ,0
Exp/Cntr=0.3,0.1

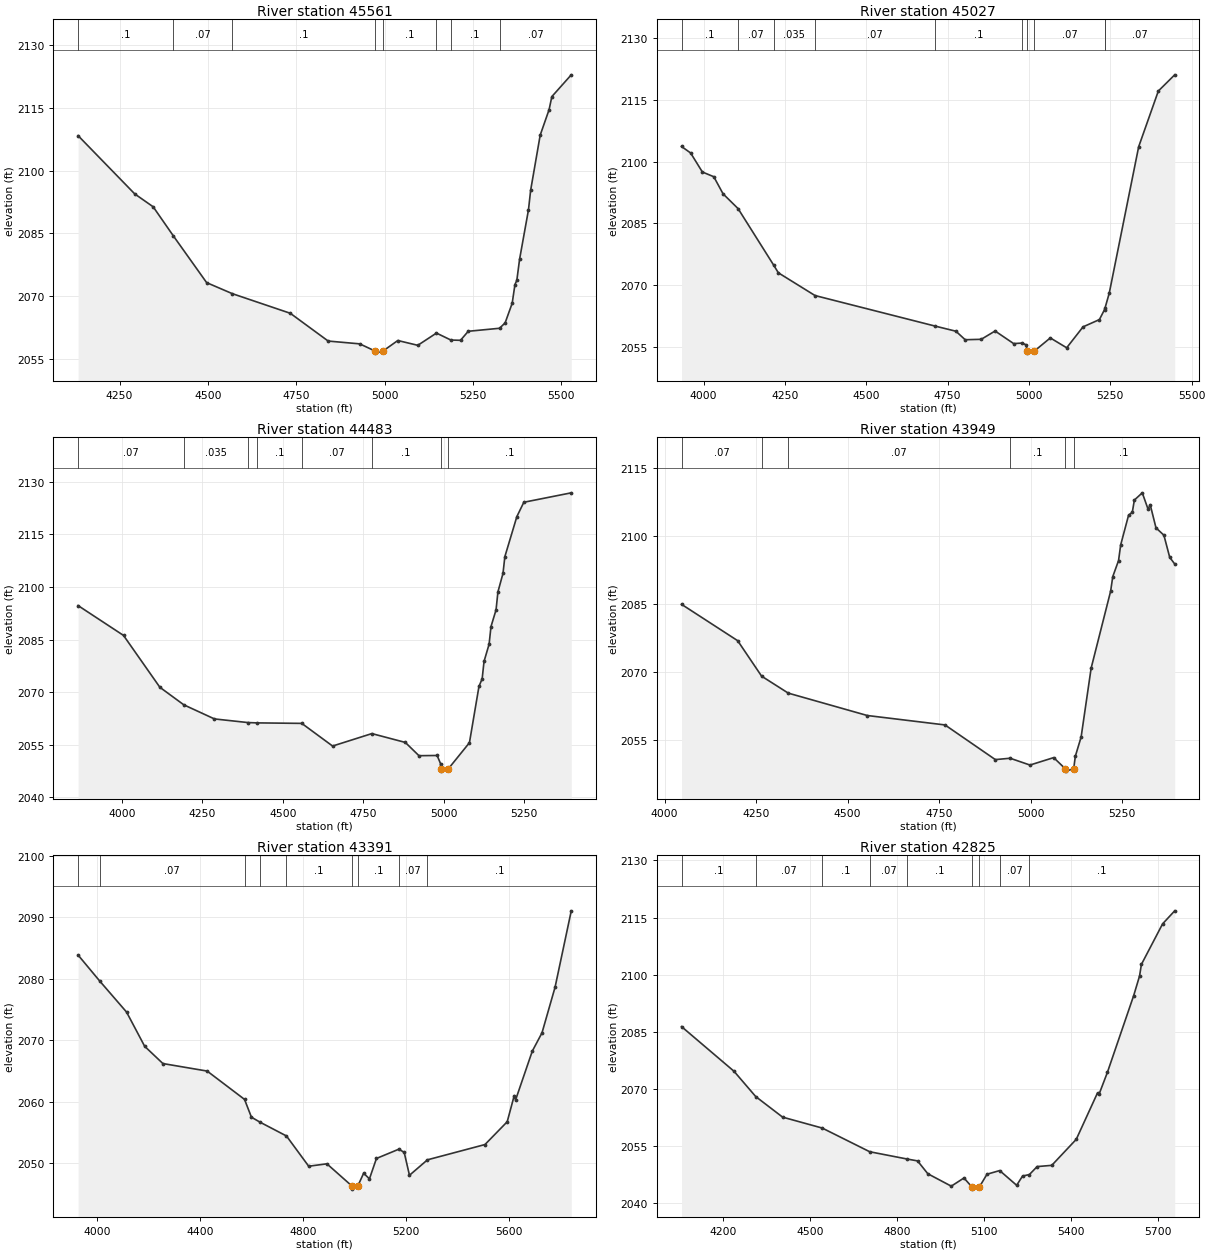
Type RM Length L Ch R = 1 ,45561   ,534,534,534
BEGIN DESCRIPTION:
Bear Creek 2 80.0
END DESCRIPTION:
XS GIS Cut Line= 3
      1810575.03     13952075.01        1809775.       13951725.
      1809274.96     13951574.99
#Sta/Elev= 30
  4132.8  2108.4  4293.1 2094.45  4345.3 2091.36  4401.6 2084.49  4496.5 2073.21
  4569.4 2070.56  4733.2 2065.87  4840.4 2059.22  4929.6 2058.55  4973.1 2056.83
  4973.6 2056.33  4995.4 2056.83  5037.4 2059.35  5093.9  2058.2  5146.7 2061.13
  5187.7 2059.46  5214.8  2059.4  5236.6 2061.56  5325.1 2062.28    5341 2063.57
    5361 2068.28  5368.8 2072.76  5374.1 2073.75  5381.9 2078.81  5407.1 2090.67
  5413.2 2095.33  5440.2 2108.52  5465.4 2114.63  5473.2 2117.75  5528.1 2122.96
#Mann= 8 ,-1 , 0
  4132.8      .1       0  4401.6     .07       0  4569.4      .1       0
  4973.1     .05       0  4995.4      .1       0  5146.7     .07       0
  5187.7      .1       0  5325.1     .07       0
Bank Sta=4973.1,4995.4
XS Rating Curve= 0 ,0
Exp/Cntr=0.3,0.1

Type RM Length L Ch R = 1 ,45027   ,544,544,544
BEGIN DESCRIPTION:
Bear Creek 2 79.0
END DESCRIPTION:
XS GIS Cut Line= 3
      1810575.01     13951925.01        1809775.       13951225.
        1809325.       13951275.
#Sta/Elev= 30
  3932.1 2103.71  3960.1 2102.13  3996.2  2097.5  4031.3 2096.35  4059.8 2092.19
  4105.9  2088.6    4215 2074.89  4229.7 2072.98  4342.4 2067.45  4710.9 2060.03
  4775.4 2058.77  4803.9  2056.7  4853.2  2056.8  4895.9 2058.82  4952.9 2055.76
  4979.2 2055.89  4991.8 2055.43  4993.9 2053.94  4994.4 2053.44  5016.5 2053.94
  5065.6 2057.14  5115.9 2054.74  5166.2 2059.83  5216.5  2061.6  5232.3 2064.04
  5233.4 2064.31  5246.7 2068.02  5337.2 2103.66  5397.6  2117.2  5447.9 2121.14
#Mann= 10 ,-1 , 0
  3932.1      .1       0  4105.9     .07       0    4215    .035       0
  4342.4     .07       0  4710.9      .1       0  4979.2     .07       0
  4993.9     .05       0  5016.5     .07       0  5232.3      .1       0
  5233.4     .07       0
Bank Sta=4993.9,5016.5
XS Rating Curve= 0 ,0
Exp/Cntr=0.3,0.1

Type RM Length L Ch R = 1 ,44483   ,534,534,534
BEGIN DESCRIPTION:
Bear Creek 2 78.0
END DESCRIPTION:
XS GIS Cut Line= 3
      1810774.99     13951574.99        1809975.       13950775.
      1809624.98     13950574.99
#Sta/Elev= 30
    3863  2094.7  4004.4 2086.19  4117.5 2071.41    4192 2066.41  4287.3 2062.39
  4391.7 2061.35  4421.1 2061.26    4559 2061.12  4654.9 2054.66  4777.1 2058.21
  4881.2 2055.69  4923.6 2051.91  4980.2 2051.97  4990.8 2049.63    4991 2048.01
  4991.5 2047.51  5013.6 2048.01  5080.7 2055.61  5110.3 2071.64  5120.3 2073.85
  5126.1 2078.78  5141.9  2083.7  5147.7  2088.7  5163.5 2093.48  5169.3 2098.59
  5185.1 2103.88  5190.9 2108.65  5228.3 2120.08  5249.9 2124.15  5397.5 2126.84
#Mann= 8 ,-1 , 0
    3863     .07       0    4192    .035       0  4391.7     .07       0
  4421.1      .1       0    4559     .07       0  4777.1      .1       0
    4991     .05       0  5013.6      .1       0
Bank Sta=4991,5013.6
XS Rating Curve= 0 ,0
Exp/Cntr=0.3,0.1

Type RM Length L Ch R = 1 ,43949   ,558,558,558
BEGIN DESCRIPTION:
Bear Creek 2 77.0
END DESCRIPTION:
XS GIS Cut Line= 3
      1810875.02     13951375.03        1810375.       13950575.
      1810175.02     13950225.04
#Sta/Elev= 30
  4046.4 2084.94  4199.7 2076.92  4265.1  2069.1  4337.9 2065.36  4553.5 2060.43
  4765.8 2058.35  4903.2 2050.71  4943.6 2051.01  4997.8 2049.51  5062.5 2051.15
  5094.4 2048.67  5094.9 2048.17  5117.1 2048.67  5121.6 2051.45  5137.4 2055.68
  5164.8 2070.88    5218 2087.84  5223.8 2091.04  5239.6 2094.58  5245.4 2098.03
    5267 2104.59  5277.1 2105.21  5282.8 2107.92  5304.4 2109.51  5320.2  2105.9
    5326  2106.9  5341.8 2101.79  5363.4 2100.17  5379.3 2095.29  5392.9 2093.83
#Mann= 6 ,-1 , 0
  4046.4     .07       0  4265.1    .035       0  4337.9     .07       0
  4943.6      .1       0  5094.4     .05       0  5117.1      .1       0
Bank Sta=5094.4,5117.1
XS Rating Curve= 0 ,0
Exp/Cntr=0.3,0.1

Type RM Length L Ch R = 1 ,43391   ,566,566,566
BEGIN DESCRIPTION:
Bear Creek 2 76.0
END DESCRIPTION:
XS GIS Cut Line= 3
      1810987.71     13951340.85        1810825.       13950275.
      1811075.01     13949474.96
#Sta/Elev= 30
  3926.3 2083.84  4010.4 2079.62  4114.7 2074.58  4185.1 2069.02  4255.9 2066.22
  4427.9    2065  4573.1  2060.4  4599.9 2057.51  4634.3 2056.68  4736.1 2054.46
  4822.4 2049.55  4893.2 2049.94  4990.6 2046.33  4991.1 2045.83  5013.3 2046.33
  5035.9 2048.41  5058.5  2047.5  5085.7 2050.81    5173 2052.32  5193.6 2051.79
    5214 2048.08    5284 2050.59  5507.4 2053.07  5593.8 2056.77  5621.1 2061.02
  5626.3 2060.31  5691.3 2068.24    5729 2071.21  5779.8 2078.62  5842.7 2091.02
#Mann= 9 ,-1 , 0
  3926.3      .1       0  4010.4     .07       0  4573.1      .1       0
  4634.3     .07       0  4736.1      .1       0  4990.6     .05       0
  5013.3      .1       0    5173     .07       0    5284      .1       0
Bank Sta=4990.6,5013.3
XS Rating Curve= 0 ,0
Exp/Cntr=0.3,0.1

Type RM Length L Ch R = 1 ,42825   ,565,565,565
BEGIN DESCRIPTION:
Bear Creek 2 75.0
END DESCRIPTION:
XS GIS Cut Line= 3
      1811775.01     13950875.02        1811275.       13950075.
      1811174.99     13949324.95
#Sta/Elev= 30
  4056.6 2086.32  4237.6 2074.57  4312.4 2067.92  4405.1 2062.51  4541.6 2059.64
  4705.4 2053.41  4834.7 2051.49  4870.3    2051  4905.7 2047.62  4986.5 2044.36
  5030.3 2046.51  5058.5 2044.08    5059 2043.58  5082.8 2044.08  5109.7  2047.5
  5153.4 2048.46  5211.9 2044.59  5232.1 2047.01  5255.9 2047.42  5282.5 2049.51
  5332.9 2049.83  5417.4 2056.68  5490.6 2068.88  5495.6 2068.47  5524.6 2074.26
  5615.4 2094.49  5635.6 2099.64  5641.9 2102.67    5715 2113.34  5756.7 2116.76
#Mann= 9 ,-1 , 0
  4056.6      .1       0  4312.4     .07       0  4541.6      .1       0
  4705.4     .07       0  4834.7      .1       0  5058.5     .05       0
  5082.8      .1       0  5153.4     .07       0  5255.9      .1       0
Bank Sta=5058.5,5082.8
XS Rating Curve= 0 ,0
Exp/Cntr=0.3,0.1

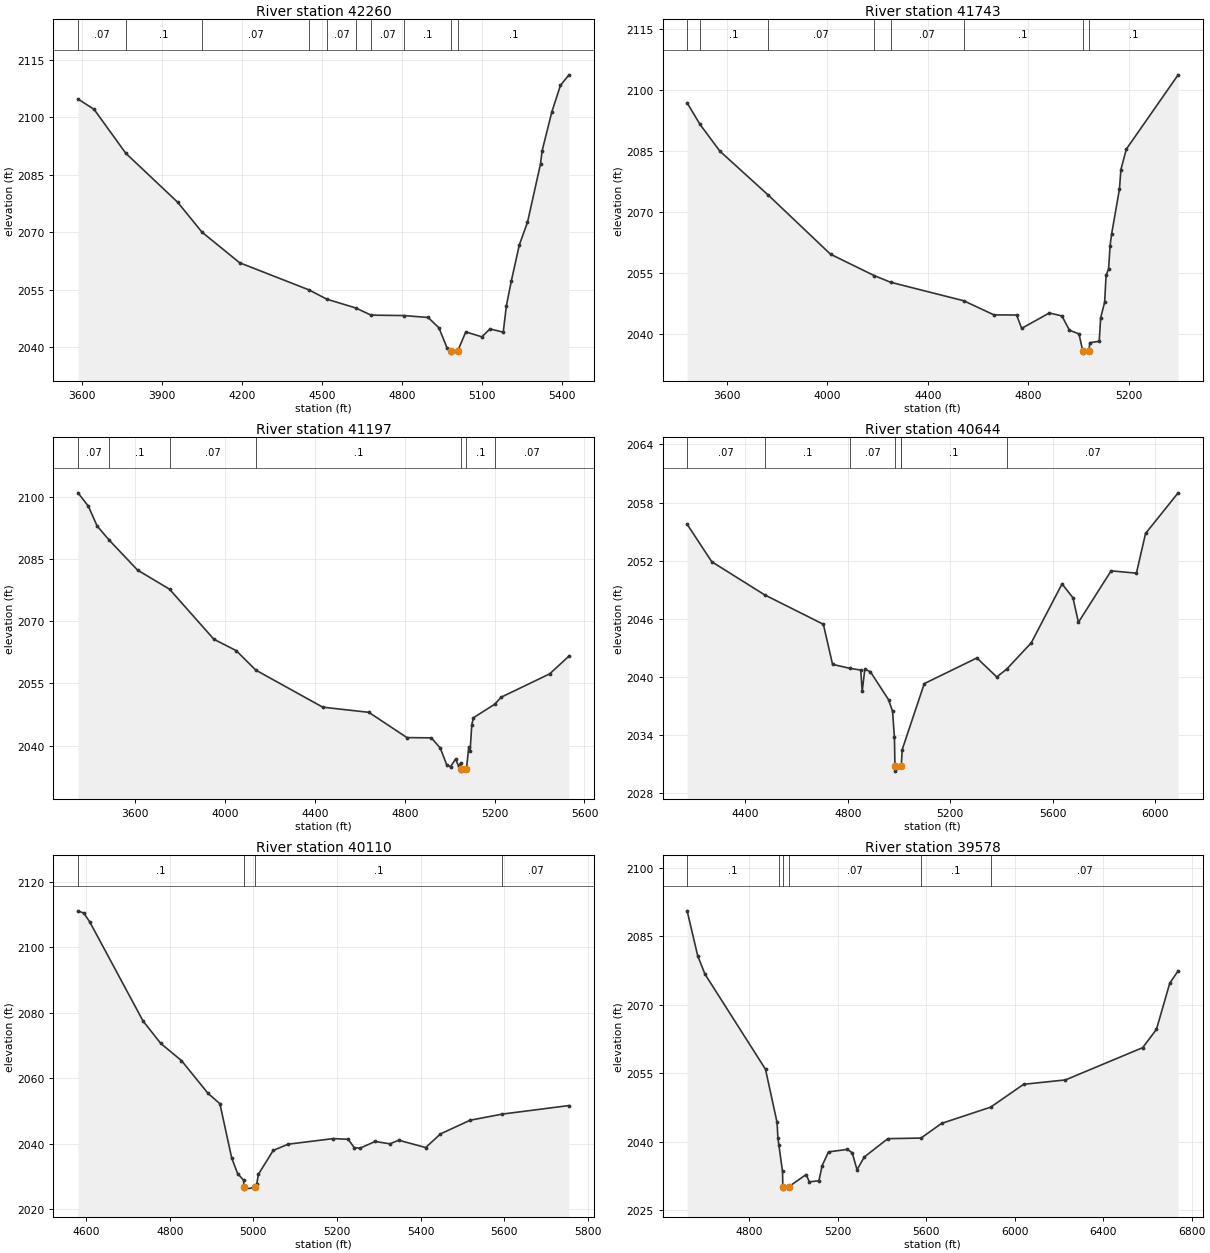
Type RM Length L Ch R = 1 ,42260   ,517,517,517
BEGIN DESCRIPTION:
Bear Creek 2 74.0
END DESCRIPTION:
XS GIS Cut Line= 3
        1811875.       13951075.        1811675.       13949675.
        1811525.     13949275.01
#Sta/Elev= 30
  3585.8 2104.73  3646.4 2102.01  3764.8 2090.61  3959.6 2077.82  4051.1 2070.01
  4191.9 2062.05  4452.8 2054.95  4518.8 2052.56    4628 2050.25  4684.9 2048.39
  4808.6 2048.28    4899 2047.78  4939.4 2045.09  4969.7 2039.88  4985.3 2038.99
  4985.8 2038.49  5009.7 2038.99  5040.1 2044.02  5100.6 2042.74  5130.8  2044.8
  5180.7 2043.95  5192.3 2050.78  5210.9 2057.27  5241.2 2066.75  5271.5 2072.56
  5320.4  2087.8  5326.6 2091.27  5363.1  2101.4  5395.2 2108.27  5427.2 2111.02
#Mann= 10 ,-1 , 0
  3585.8     .07       0  3764.8      .1       0  4051.1     .07       0
  4452.8      .1       0  4518.8     .07       0    4628      .1       0
  4684.9     .07       0  4808.6      .1       0  4985.3     .05       0
  5009.7      .1       0
Bank Sta=4985.3,5009.7
XS Rating Curve= 0 ,0
Exp/Cntr=0.3,0.1

Type RM Length L Ch R = 1 ,41743   ,546,546,546
BEGIN DESCRIPTION:
Bear Creek 2 73.0
END DESCRIPTION:
XS GIS Cut Line= 3
        1811925.     13950925.01        1812025.       13949375.
      1811675.04     13949175.02
#Sta/Elev= 30
  3441.3 2096.92  3492.9  2091.6  3571.6 2085.05  3762.7 2074.33  4012.5 2059.68
  4185.9 2054.44  4252.5 2052.77  4542.8 2048.23  4663.9 2044.75    4754 2044.72
  4774.1 2041.43  4884.3 2045.22  4934.4 2044.49  4964.5 2040.98  5002.5 2040.07
  5017.6 2035.84  5018.1 2035.34    5042 2035.84  5045.6  2037.9  5083.1 2038.26
  5088.8 2044.03  5104.7 2047.88  5110.4 2054.47  5120.5  2056.1  5126.3 2061.73
  5132.7 2064.73  5163.7  2075.7  5169.5  2080.5  5191.1 2085.54  5397.6 2103.82
#Mann= 8 ,-1 , 0
  3441.3     .07       0  3492.9      .1       0  3762.7     .07       0
  4185.9      .1       0  4252.5     .07       0  4542.8      .1       0
  5017.6     .05       0    5042      .1       0
Bank Sta=5017.6,5042
XS Rating Curve= 0 ,0
Exp/Cntr=0.3,0.1

Type RM Length L Ch R = 1 ,41197   ,553,553,553
BEGIN DESCRIPTION:
Bear Creek 2 72.0
END DESCRIPTION:
XS GIS Cut Line= 3
        1811975.     13950974.99        1812525.       13949425.
        1812225.     13948975.01
#Sta/Elev= 30
  3345.5 2101.05  3391.8 2097.83  3430.4 2093.06  3485.2 2089.58  3610.8 2082.38
    3753 2077.77  3950.3 2065.68  4049.7 2062.93  4137.3 2058.21    4435 2049.26
    4640 2048.02  4809.8 2041.91  4918.3 2041.85  4958.3 2039.37  4987.5 2035.24
  5003.7 2034.88  5026.2 2036.71  5039.8    2035  5048.8 2035.77    5050 2034.31
  5050.5 2033.81  5074.6 2034.31  5084.8 2039.56  5090.8 2038.58  5098.3    2045
  5105.9 2046.72  5201.2    2050    5229 2051.67  5445.4 2057.32    5531 2061.61
#Mann= 7 ,-1 , 0
  3345.5     .07       0  3485.2      .1       0    3753     .07       0
  4137.3      .1       0    5050     .05       0  5074.6      .1       0
  5201.2     .07       0
Bank Sta=5050,5074.6
XS Rating Curve= 0 ,0
Exp/Cntr=0.3,0.1

Type RM Length L Ch R = 1 ,40644   ,534,534,534
BEGIN DESCRIPTION:
Bear Creek 2 71.0
END DESCRIPTION:
XS GIS Cut Line= 3
      1812616.21     13950298.64      1813064.28     13949506.78
      1812375.02     13948775.02
#Sta/Elev= 30
  4173.4 2055.75  4269.5 2051.88  4475.7 2048.46  4704.7 2045.42  4740.6 2041.28
  4808.1 2040.87  4850.5 2040.69  4856.2 2038.48  4866.4 2040.79    4888 2040.52
  4958.9 2037.63  4974.6 2036.43  4981.9 2033.74  4983.9 2030.75  4984.4 2030.25
  5008.5 2030.75  5008.7 2030.85  5012.1 2032.47  5098.3 2039.29  5303.4 2041.94
  5381.1 2039.98  5419.5 2040.78  5515.4  2043.5  5635.6 2049.59  5678.1 2048.16
  5699.5 2045.62    5827 2050.94  5925.7  2050.7  5961.3  2054.8  6088.5    2059
#Mann= 7 ,-1 , 0
  4173.4     .07       0  4475.7      .1       0  4808.1     .07       0
  4983.9     .05       0  5008.5     .07       0  5008.7      .1       0
  5419.5     .07       0
Bank Sta=4983.9,5008.5
XS Rating Curve= 0 ,0
Exp/Cntr=0.3,0.1

Type RM Length L Ch R = 1 ,40110   ,532,532,532
BEGIN DESCRIPTION:
Bear Creek 2 70.0
END DESCRIPTION:
XS GIS Cut Line= 3
      1813675.01     13949625.01        1813375.       13949325.
      1812774.98     13948874.98
#Sta/Elev= 30
  4580.5 2111.07  4594.6 2110.34  4608.8 2107.66  4736.1 2077.44  4778.5 2070.58
    4828 2065.35  4891.6 2055.33  4919.9 2052.18  4948.2 2035.58  4962.3 2030.85
  4976.5 2028.81  4977.8 2026.59  4978.3 2026.09  5003.5 2026.59  5007.9 2027.57
  5012.1 2030.65  5047.5 2037.91  5082.9 2039.81  5191.2 2041.52  5226.6 2041.31
  5241.2 2038.78  5254.8 2038.58  5291.2 2040.64  5326.6 2039.92  5347.5 2041.03
  5412.1 2038.79  5447.5 2042.95  5518.3 2047.13  5595.7 2049.01  5754.8 2051.61
#Mann= 4 ,-1 , 0
  4580.5      .1       0  4977.8     .05       0  5003.5      .1       0
  5595.7     .07       0
Bank Sta=4977.8,5003.5
XS Rating Curve= 0 ,0
Exp/Cntr=0.3,0.1

Type RM Length L Ch R = 1 ,39578   ,614,614,614
BEGIN DESCRIPTION:
Bear Creek 2 69.0
END DESCRIPTION:
XS GIS Cut Line= 4
        1813825.     13949425.02      1813784.55     13949020.55
      1813665.79     13948877.22      1812175.04     13948225.02
#Sta/Elev= 30
  4519.3 2090.53  4567.1 2080.68  4599.7 2076.69  4873.6 2055.83  4925.8 2044.21
  4929.7 2040.69  4934.1  2039.2  4950.5 2033.49    4952  2030.1  4952.5  2029.6
  4977.8  2030.1  5057.3 2032.79  5071.7  2031.2  5115.1 2031.43  5129.6 2034.75
  5158.4 2037.75  5243.8  2038.3  5265.6 2037.55  5287.4 2033.84  5320.2 2036.64
  5426.6 2040.65  5576.7 2040.78  5669.5 2043.99  5891.5 2047.55  6040.6 2052.55
  6229.6 2053.51  6578.9 2060.58  6640.9 2064.58  6701.3 2074.71  6739.1 2077.39
#Mann= 6 ,-1 , 0
  4519.3      .1       0  4934.1     .07       0    4952     .05       0
  4977.8     .07       0  5576.7      .1       0  5891.5     .07       0
Bank Sta=4952,4977.8
XS Rating Curve= 0 ,0
Exp/Cntr=0.3,0.1

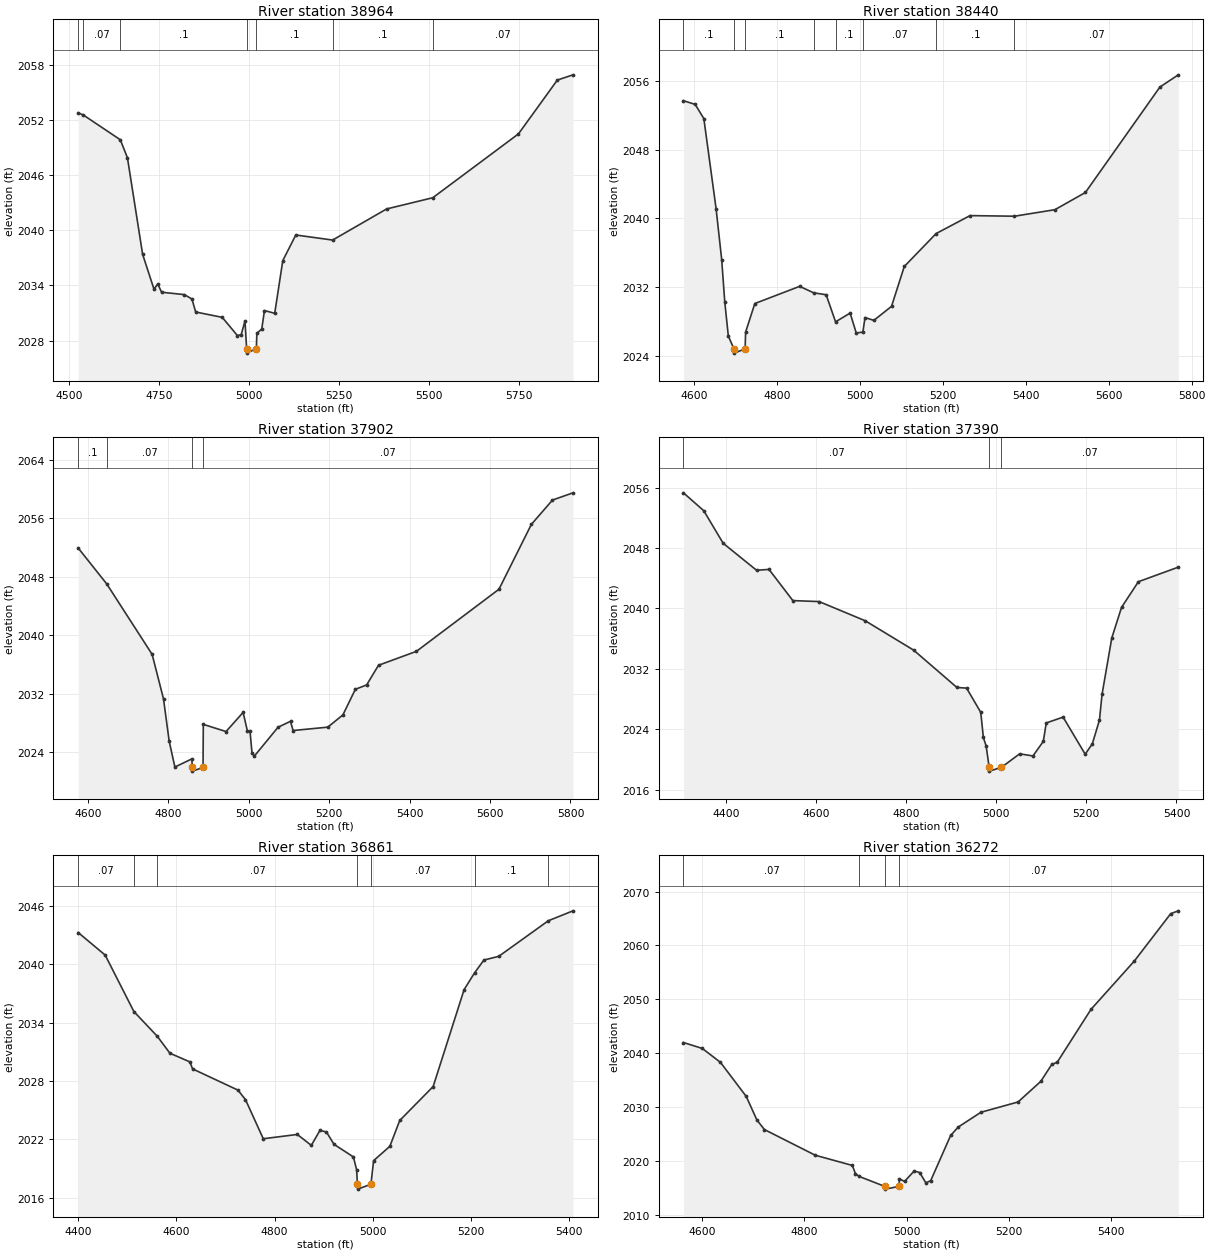
Type RM Length L Ch R = 1 ,38964   ,524,524,524
BEGIN DESCRIPTION:
Bear Creek 2 68.0
END DESCRIPTION:
XS GIS Cut Line= 3
      1814424.96     13948624.99        1813975.       13948475.
      1813224.99     13947974.99
#Sta/Elev= 30
  4525.3 2052.75  4539.8 2052.51  4642.5 2049.82  4662.3 2047.86  4704.5 2037.37
  4736.1 2033.58  4746.6 2034.15  4757.2 2033.25  4820.4 2032.99  4841.5 2032.52
    4852  2031.1  4925.8 2030.52    4968 2028.54  4978.5 2028.64  4989.1 2030.13
  4993.6 2027.13  4994.1 2026.63  5020.6 2027.13  5022.1 2028.79  5035.7 2029.25
  5043.2 2031.26  5071.7 2030.96  5094.2 2036.69  5130.3 2039.47  5232.7 2038.92
  5382.7  2042.3  5511.1 2043.52  5749.3 2050.46  5857.4 2056.31    5901 2056.88
#Mann= 7 ,-1 , 0
  4525.3      .1       0  4539.8     .07       0  4642.5      .1       0
  4993.6     .05       0  5020.6      .1       0  5232.7      .1       0
  5511.1     .07       0
Bank Sta=4993.6,5020.6
XS Rating Curve= 0 ,0
Exp/Cntr=0.3,0.1

Type RM Length L Ch R = 1 ,38440   ,538,538,538
BEGIN DESCRIPTION:
Bear Creek 2 67.0
END DESCRIPTION:
XS GIS Cut Line= 3
      1814475.01     13948275.01        1814125.       13948025.
      1813475.04     13947625.02
#Sta/Elev= 30
  4574.6  2053.7  4602.9 2053.27  4623.8 2051.61  4653.3 2041.14  4666.8 2035.21
  4674.2  2030.3  4682.8 2026.32  4696.3 2024.83  4696.8 2024.33  4723.3 2024.83
  4724.5 2026.78  4746.7  2030.1  4854.8  2032.1  4888.5 2031.35  4918.7 2031.12
  4941.4 2027.97  4976.5 2028.99  4991.2 2026.68  5007.2 2026.77  5012.4 2028.47
  5033.7 2028.14  5076.3 2029.77  5107.1 2034.41  5183.8 2038.24  5265.6 2040.33
  5372.8 2040.26  5470.4 2041.02  5543.8 2043.02  5723.5 2055.29  5767.9 2056.71
#Mann= 8 ,-1 , 0
  4574.6      .1       0  4696.3     .05       0  4723.3      .1       0
  4888.5     .07       0  4941.4      .1       0  5007.2     .07       0
  5183.8      .1       0  5372.8     .07       0
Bank Sta=4696.3,4723.3
XS Rating Curve= 0 ,0
Exp/Cntr=0.3,0.1

Type RM Length L Ch R = 1 ,37902   ,512,512,512
BEGIN DESCRIPTION:
Bear Creek 2 66.0
END DESCRIPTION:
XS GIS Cut Line= 3
      1814675.03     13947875.03        1814375.       13947575.
      1813675.03     13947175.02
#Sta/Elev= 30
  4575.9 2051.93  4646.8 2047.02  4759.8 2037.37  4788.1 2031.27  4802.2 2025.49
  4816.4 2021.94  4858.8 2023.06  4859.4 2021.88  4859.9 2021.38  4886.4 2021.88
  4887.1 2027.78  4943.6  2026.8  4986.1 2029.42  4996.7 2026.88  5003.1 2026.88
  5008.1 2023.93  5013.9 2023.43  5072.9 2027.39  5103.9  2028.2  5110.3 2026.94
  5196.7  2027.4  5234.2 2029.08  5265.1 2032.58  5293.2 2033.18  5322.7 2035.87
    5417 2037.78  5622.2 2046.28  5702.8 2055.16  5755.3 2058.49  5806.4 2059.48
#Mann= 4 ,-1 , 0
  4575.9      .1       0  4646.8     .07       0  4859.4     .05       0
  4886.4     .07       0
Bank Sta=4859.4,4886.4
XS Rating Curve= 0 ,0
Exp/Cntr=0.3,0.1

Type RM Length L Ch R = 1 ,37390   ,529,529,529
BEGIN DESCRIPTION:
Bear Creek 2 65.0
END DESCRIPTION:
XS GIS Cut Line= 3
      1814975.01     13947775.02        1814625.       13947175.
      1814274.97     13946974.98
#Sta/Elev= 30
  4306.3 2055.31  4351.4 2052.94  4394.4 2048.63  4468.4 2045.06  4496.1 2045.17
    4549 2041.04  4607.3 2040.91  4709.5 2038.37    4817 2034.48  4912.9 2029.54
  4934.4 2029.45  4965.8 2026.25  4971.6 2022.92  4977.8 2021.78  4984.5 2018.96
    4985 2018.46  5011.6 2018.96  5052.1 2020.75  5081.6 2020.47  5104.6  2022.4
  5111.1 2024.84  5148.5 2025.61  5197.5  2020.7  5213.3 2022.07  5229.1 2025.21
  5234.9 2028.63  5256.5 2036.09  5278.1 2040.14  5315.5 2043.54  5404.1 2045.47
#Mann= 3 ,-1 , 0
  4306.3     .07       0  4984.5     .05       0  5011.6     .07       0
Bank Sta=4984.5,5011.6
XS Rating Curve= 0 ,0
Exp/Cntr=0.3,0.1

Type RM Length L Ch R = 1 ,36861   ,589,589,589
BEGIN DESCRIPTION:
Bear Creek 2 64.0
END DESCRIPTION:
XS GIS Cut Line= 3
      1815225.03     13946975.01        1814675.       13946725.
        1814275.       13946675.
#Sta/Elev= 30
  4400.1 2043.26  4455.1 2040.94  4513.5 2035.14  4561.2 2032.59  4586.9 2030.85
  4627.5 2029.96    4633 2029.24  4725.3 2027.06  4740.7 2026.08  4776.9 2022.06
  4846.1  2022.5  4874.7 2021.38  4892.2 2022.91  4905.4 2022.76  4920.8 2021.49
  4960.3 2020.19  4966.9 2018.88  4968.6 2017.38  4969.1 2016.88    4996 2017.38
  5001.5 2019.81  5034.5 2021.28  5054.7 2023.94  5122.7 2027.43  5185.7 2037.39
  5207.2 2039.13    5226 2040.43  5256.2 2040.81  5357.1 2044.47  5407.4 2045.49
#Mann= 7 ,-1 , 0
  4400.1     .07       0  4513.5      .1       0  4561.2     .07       0
  4968.6     .05       0    4996     .07       0  5207.2      .1       0
  5357.1     .07       0
Bank Sta=4968.6,4996
XS Rating Curve= 0 ,0
Exp/Cntr=0.3,0.1

Type RM Length L Ch R = 1 ,36272   ,520,520,520
BEGIN DESCRIPTION:
Bear Creek 2 63.0
END DESCRIPTION:
XS GIS Cut Line= 3
      1815425.02     13946575.01        1815075.       13946325.
      1814874.98     13945824.96
#Sta/Elev= 30
  4563.1 2041.98    4600 2040.88  4635.6 2038.29    4686 2031.97  4706.9 2027.59
  4721.6 2025.82  4821.2 2021.05  4893.7 2019.16  4899.8 2017.62  4907.3 2017.11
  4957.3 2015.26  4957.8 2014.76  4984.9 2015.26  4985.9 2016.67  4995.9 2016.19
  5014.8 2018.13  5025.5 2017.84  5037.7 2015.91  5047.1 2016.34  5086.1 2024.72
  5100.9 2026.28  5145.4 2029.03  5218.1 2030.94  5262.5 2034.76    5284  2037.9
  5294.8 2038.33  5360.8 2048.13  5445.6  2057.1  5516.9  2065.9  5531.8 2066.43
#Mann= 4 ,-1 , 0
  4563.1     .07       0  4907.3      .1       0  4957.3     .05       0
  4984.9     .07       0
Bank Sta=4957.3,4984.9
XS Rating Curve= 0 ,0
Exp/Cntr=0.3,0.1

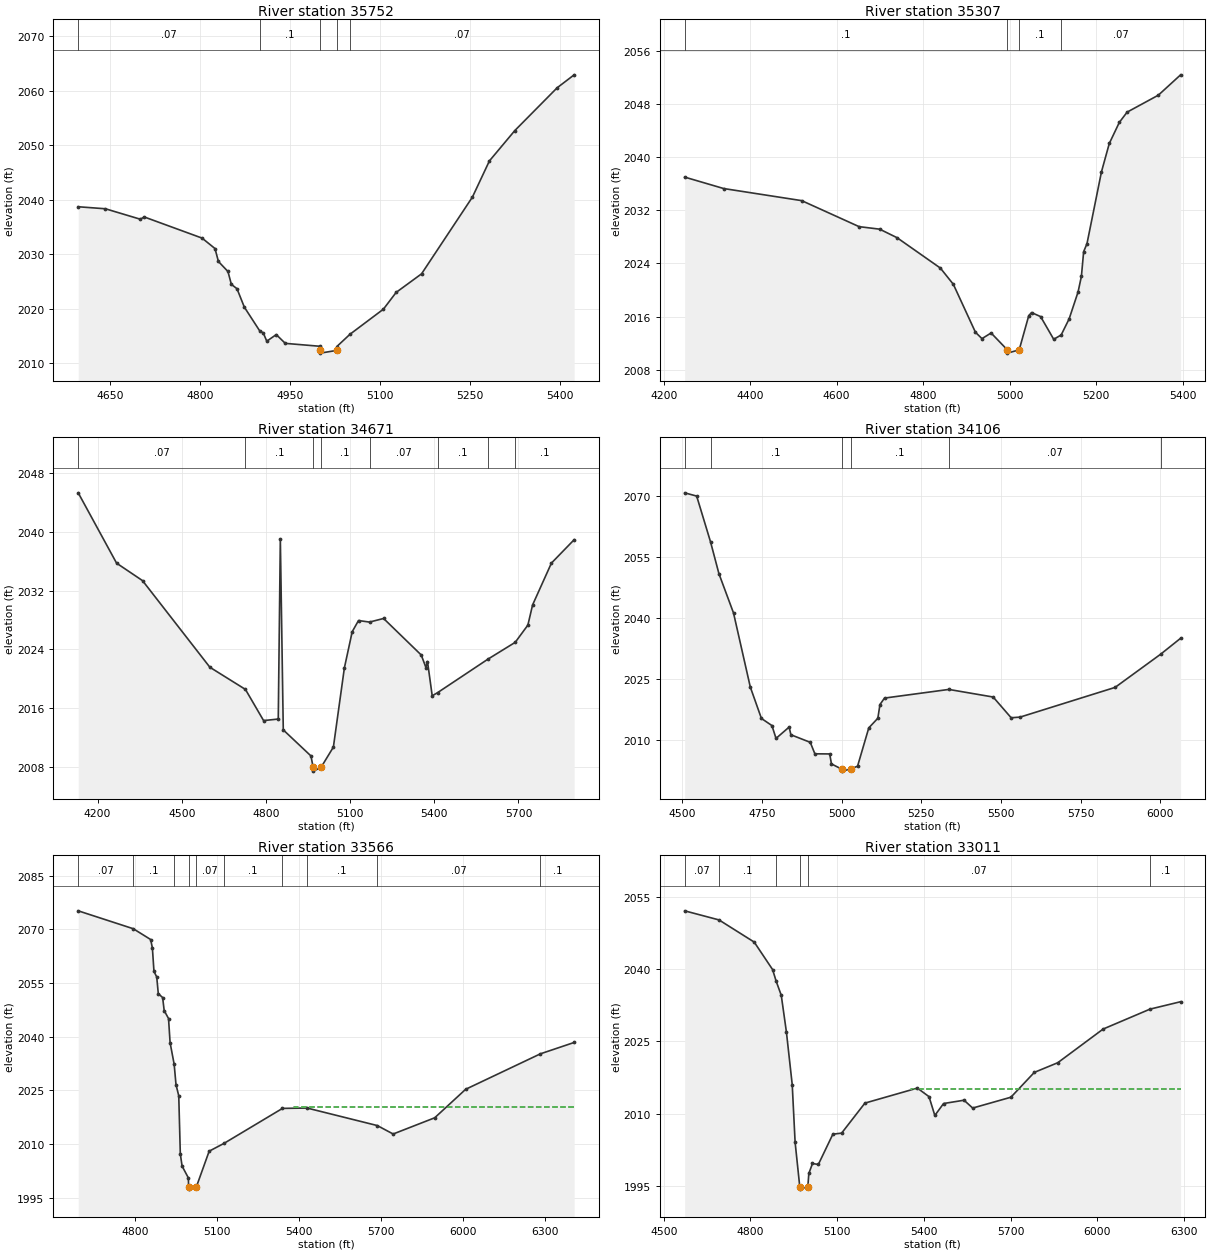
Type RM Length L Ch R = 1 ,35752   ,445,445,445
BEGIN DESCRIPTION:
Bear Creek 2 62.0
END DESCRIPTION:
XS GIS Cut Line= 3
        1815575.       13946375.        1815375.       13946025.
      1815074.98     13945724.98
#Sta/Elev= 30
  4596.9 2038.75  4642.3 2038.38  4700.6 2036.46    4707 2036.88  4803.5    2033
  4825.1 2031.08  4830.8 2028.71  4846.7 2026.87  4852.4 2024.51  4861.8 2023.71
    4874 2020.34  4899.5 2016.01  4905.7 2015.58  4911.5 2014.08  4927.3 2015.29
  4942.4 2013.68    5000 2013.15  5000.4 2012.39  5000.9 2011.89    5028 2012.39
  5028.3 2013.09  5050.4 2015.36  5106.1 2019.96  5127.3 2023.03  5169.7 2026.44
  5254.6 2040.53  5282.9 2047.16  5325.3 2052.73    5396 2060.59  5424.3 2062.96
#Mann= 5 ,-1 , 0
  4596.9     .07       0  4899.5      .1       0  5000.4     .05       0
    5028      .1       0  5050.4     .07       0
Bank Sta=5000.4,5028
XS Rating Curve= 0 ,0
Exp/Cntr=0.3,0.1

Type RM Length L Ch R = 1 ,35307   ,636,636,636
BEGIN DESCRIPTION:
Bear Creek 2 61.0
END DESCRIPTION:
XS GIS Cut Line= 4
        1815725.     13946475.03      1815765.32     13945829.95
      1815642.49     13945641.87      1815374.99       13945575.
#Sta/Elev= 30
  4248.6 2036.98  4338.8 2035.26  4519.2 2033.44  4651.9 2029.53  4699.5 2029.15
  4739.6 2027.87  4839.8  2023.3  4869.8 2020.86  4920.9 2013.65    4936 2012.69
  4957.1 2013.54  4994.5 2011.01    4995 2010.51  5022.1 2011.01  5044.2 2016.15
  5050.6 2016.61  5071.6    2016  5101.9 2012.59  5119.1 2013.24  5137.6 2015.67
  5158.2 2019.71  5165.9 2022.06  5171.1 2025.77  5178.8 2026.97  5212.3 2037.78
  5230.4 2042.04  5253.6 2045.21  5271.6 2046.75  5343.8  2049.3  5395.3 2052.36
#Mann= 4 ,-1 , 0
  4248.6      .1       0  4994.5     .05       0  5022.1      .1       0
  5119.1     .07       0
Bank Sta=4994.5,5022.1
XS Rating Curve= 0 ,0
Exp/Cntr=0.3,0.1

Type RM Length L Ch R = 1 ,34671   ,565,565,565
BEGIN DESCRIPTION:
Bear Creek 2 60.0
END DESCRIPTION:
XS GIS Cut Line= 3
        1816575.     13946224.99        1816225.       13945425.
      1815825.01     13944625.03
#Sta/Elev= 30
  4130.9 2045.33  4267.7 2035.74  4360.1 2033.36  4600.2 2021.55  4726.9 2018.53
  4791.6 2014.28  4843.9 2014.49  4851.3 2039.02  4861.8 2013.01  4960.4 2009.46
  4968.4 2007.89  4968.9 2007.39  4996.2 2007.89  5040.4 2010.67  5079.6 2021.47
  5107.5  2026.4  5129.9 2027.92  5169.1 2027.71  5219.3  2028.2  5353.5 2023.22
  5370.3 2021.51  5375.8 2022.33  5392.6 2017.66  5412.2  2018.1  5591.8 2022.67
  5688.5 2024.95  5733.6  2027.3  5750.4 2030.05  5817.5 2035.75  5898.5 2038.94
#Mann= 8 ,-1 , 0
  4130.9     .07       0  4726.9      .1       0  4968.4     .05       0
  4996.2      .1       0  5169.1     .07       0  5412.2      .1       0
  5591.8     .07       0  5688.5      .1       0
Bank Sta=4968.4,4996.2
XS Rating Curve= 0 ,0
Exp/Cntr=0.3,0.1

Type RM Length L Ch R = 1 ,34106   ,540,540,540
BEGIN DESCRIPTION:
Bear Creek 2 59.0
END DESCRIPTION:
XS GIS Cut Line= 3
      1817224.97     13945574.99        1816775.       13945375.
      1815975.02     13944675.02
#Sta/Elev= 30
  4507.8 2070.83  4545.4 2070.03  4588.9 2058.76  4615.2 2050.94    4661 2041.26
  4713.6 2023.05  4748.5 2015.32  4781.4 2013.57  4794.3 2010.41  4835.4  2013.2
  4840.9 2011.31  4901.7 2009.44  4916.1 2006.62  4962.6 2006.59  4968.1 2004.14
    5000 2002.86  5000.5 2002.36  5027.9 2002.86    5050 2003.58  5085.2    2013
  5113.6 2015.37  5120.3 2018.75  5134.5 2020.33  5336.3 2022.46  5475.3 2020.59
  5531.7 2015.49  5559.7 2015.65  5857.7 2022.96  6000.8 2031.14  6063.2 2035.05
#Mann= 6 ,-1 , 0
  4507.8     .07       0  4588.9      .1       0    5000     .05       0
  5027.9      .1       0  5336.3     .07       0  6000.8      .1       0
#XS Ineff= 2 , 0
                          5300.9         2022.04
Permanent Ineff=
       F       F
Bank Sta=5000,5027.9
XS Rating Curve= 0 ,0
Exp/Cntr=0.3,0.1

Type RM Length L Ch R = 1 ,33566   ,555,555,555
BEGIN DESCRIPTION:
Bear Creek 2 58.0
END DESCRIPTION:
XS GIS Cut Line= 3
      1817425.02     13945475.04        1817225.       13945125.
      1815925.02     13944575.01
#Sta/Elev= 30
    4593  2075.2  4794.6 2070.19    4858 2067.18  4864.4 2064.84  4870.2 2058.26
  4880.3 2056.71    4886 2052.06  4901.9 2050.95  4907.6  2047.3  4923.5 2045.09
  4929.2 2038.34  4944.1 2032.31  4950.8 2026.63  4960.9 2023.48  4966.6 2007.25
  4973.1 2003.84  4996.2 2000.52  4996.8  1997.9  4997.3  1997.4  5024.7  1997.9
  5072.2 2008.01  5126.3 2010.18  5340.4 2019.97  5430.4 2020.07  5687.4 2015.17
  5745.4 2012.81  5897.4 2017.34  6010.7 2025.31  6284.4 2035.23  6407.7  2038.4
#Mann= 10 ,-1 , 0
    4593     .07       0  4794.6      .1       0  4944.1     .07       0
  4996.8     .05       0  5024.7     .07       0  5126.3      .1       0
  5340.4     .07       0  5430.4      .1       0  5687.4     .07       0
  6284.4      .1       0
#XS Ineff= 2 , 0
                         5383.12         2020.32
Permanent Ineff=
       F       F
Bank Sta=4996.8,5024.7
XS Rating Curve= 0 ,0
Exp/Cntr=0.3,0.1

Type RM Length L Ch R = 1 ,33011   ,527,527,527
BEGIN DESCRIPTION:
Bear Creek 2 57.0
END DESCRIPTION:
XS GIS Cut Line= 4
      1817575.02     13944825.02      1817355.48     13944618.52
        1817225.       13944625.      1815951.25     13944467.44
#Sta/Elev= 30
  4572.6 2052.14  4691.3 2050.25  4813.2 2045.64  4876.7 2039.93    4889 2037.53
  4906.7 2034.58  4924.5 2026.96  4944.6 2016.02  4954.6 2004.03  4970.7  1994.8
  4971.2  1994.3  4998.6  1994.8  5002.1 1997.55  5014.7 1999.63  5034.9 1999.42
  5085.2 2005.72  5115.5 2005.94  5196.1 2012.18  5377.5  2015.3  5417.8 2013.52
  5437.9 2009.61  5468.1 2012.09  5538.9 2012.78  5568.9 2011.15    5701  2013.4
    5782 2018.56  5863.1 2020.57  6020.1 2027.57  6182.2 2031.71  6288.1 2033.25
#Mann= 6 ,-1 , 0
  4572.6     .07       0  4691.3      .1       0    4889     .07       0
  4970.7     .05       0  4998.6     .07       0  6182.2      .1       0
#XS Ineff= 2 , 0
                         5355.04         2015.15
Permanent Ineff=
       F       F
Bank Sta=4970.7,4998.6
XS Rating Curve= 0 ,0
Exp/Cntr=0.3,0.1