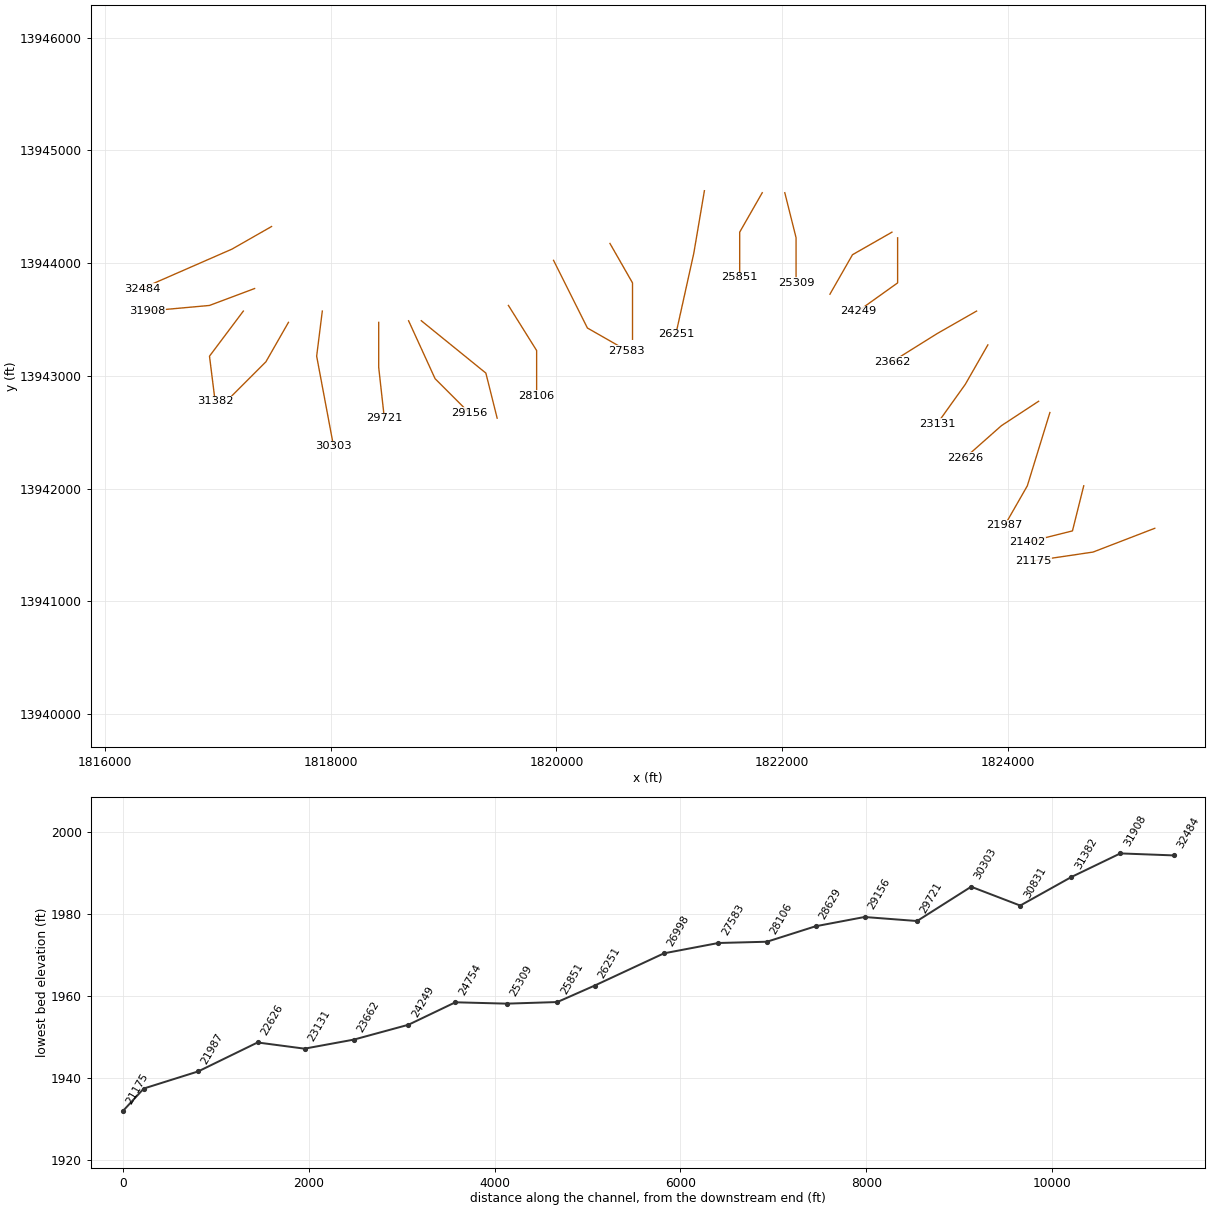
HEC-RAS study Bear Creek 2.prj: Bear Creek 2 Base Level Engineering

--- Bear Creek 2.g01 (geometry) --- (continued)

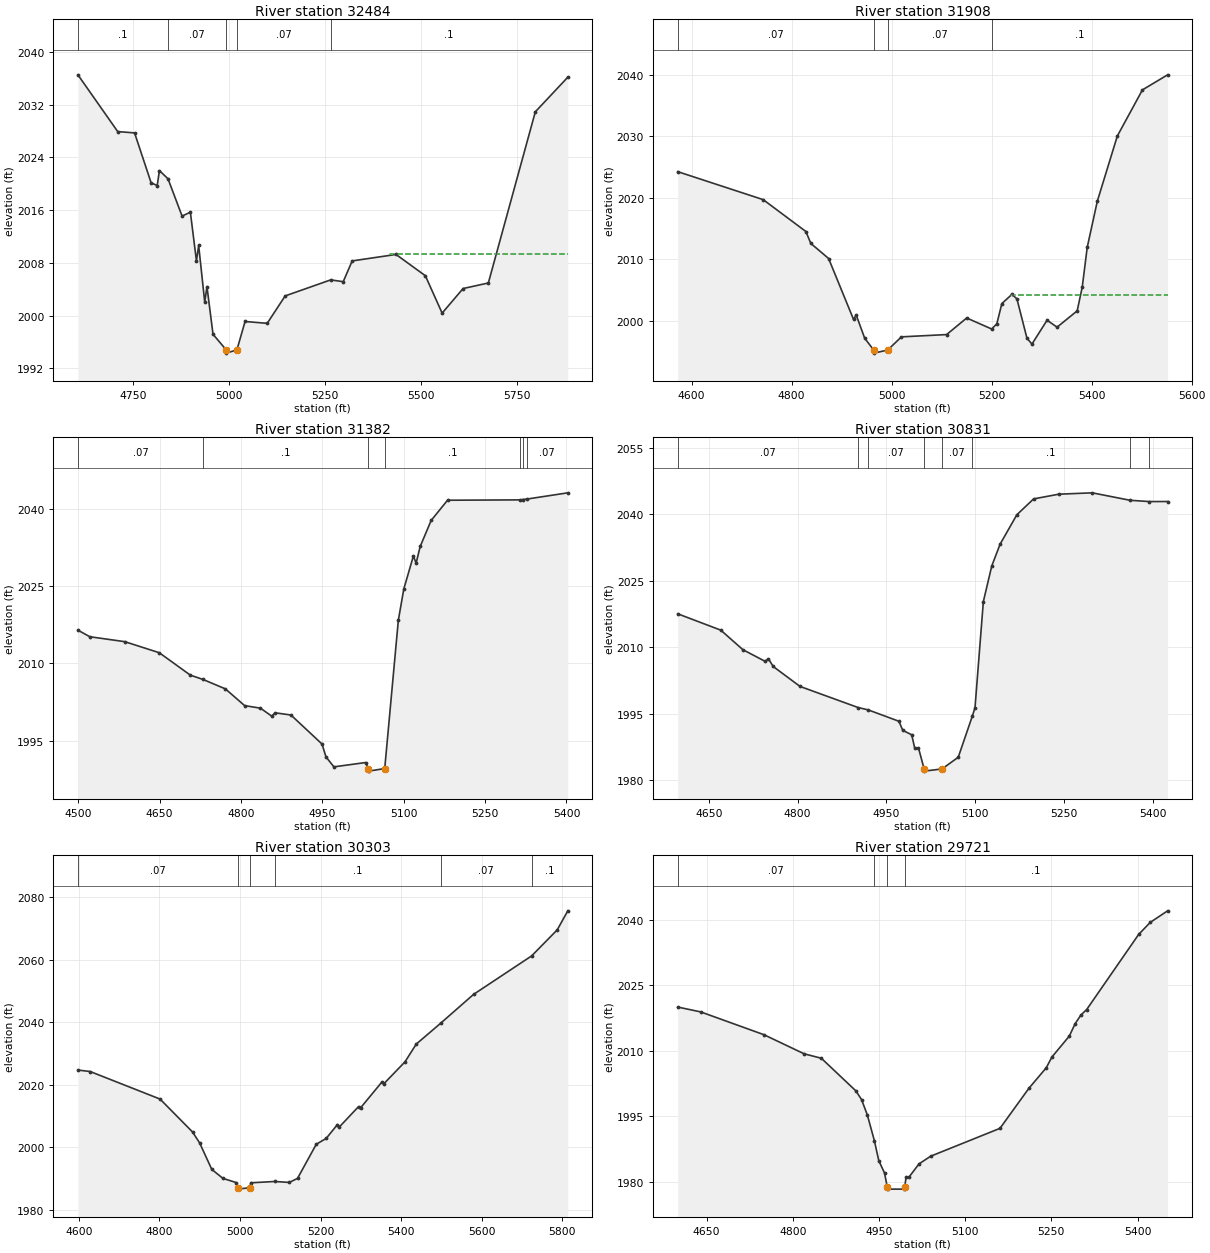
Type RM Length L Ch R = 1 ,32484   ,576,576,576
BEGIN DESCRIPTION:
Bear Creek 2 56.0
END DESCRIPTION:
XS GIS Cut Line= 3
      1817475.01     13944325.01        1817125.       13944125.
      1816325.04     13943775.02
#Sta/Elev= 30
  4605.4 2036.53  4709.1 2027.92    4753 2027.72  4796.2 2020.14    4812 2019.74
  4817.8    2022  4840.1 2020.76  4876.8  2015.1  4898.4 2015.69  4914.2 2008.31
    4920 2010.64  4935.8 2002.05  4941.6  2004.4  4957.4 1997.17  4991.7 1994.81
  4992.2 1994.31  5019.7 1994.81  5040.9 1999.11  5098.6 1998.83  5145.4 2002.99
  5263.9 2005.42  5296.6 2005.15    5320  2008.3  5434.2 2009.28  5510.6 2006.05
  5554.3 2000.38  5608.9 2004.11  5674.7 2004.95  5797.1 2030.92  5881.7 2036.17
#Mann= 5 ,-1 , 0
  4605.4      .1       0  4840.1     .07       0  4991.7     .05       0
  5019.7     .07       0  5263.9      .1       0
#XS Ineff= 2 , 0
         4920.28 2010.46 5418.18         2009.36
Permanent Ineff=
       F       F
Bank Sta=4991.7,5019.7
XS Rating Curve= 0 ,0
Exp/Cntr=0.3,0.1

Type RM Length L Ch R = 1 ,31908   ,526,526,526
BEGIN DESCRIPTION:
Bear Creek 2 55.0
END DESCRIPTION:
XS GIS Cut Line= 3
      1817324.99       13943775.        1816925.       13943625.
      1816374.95       13943575.
#Sta/Elev= 30
  4572.4 2024.24  4743.3  2019.7  4828.7 2014.53  4838.5  2012.6  4874.1 2010.15
  4923.9 2000.27  4929.3 2000.97  4946.2 1997.23  4964.2  1995.3  4964.7  1994.8
  4992.2  1995.3  5019.7 1997.44    5110 1997.81  5150.2  2000.5  5200.2 1998.71
  5210.5 1999.57  5220.5 2002.84  5240.6 2004.33  5250.6 2003.61  5270.7 1997.21
  5280.7 1996.27  5310.9 2000.14  5330.9 1999.01  5371.1 2001.66  5381.2  2005.5
  5391.2 2011.97  5411.3 2019.43  5451.4 2030.03  5501.6 2037.51  5551.9 2039.95
#Mann= 4 ,-1 , 0
  4572.4     .07       0  4964.2     .05       0  4992.2     .07       0
  5200.2      .1       0
#XS Ineff= 2 , 0
                         5237.96         2004.27
Permanent Ineff=
       F       F
Bank Sta=4964.2,4992.2
XS Rating Curve= 0 ,0
Exp/Cntr=0.3,0.1

Type RM Length L Ch R = 1 ,31382   ,551,551,551
BEGIN DESCRIPTION:
Bear Creek 2 54.0
END DESCRIPTION:
XS GIS Cut Line= 3
      1817225.02     13943575.02        1816925.       13943175.
        1816975.     13942775.04
#Sta/Elev= 30
  4499.4 2016.46  4521.3 2015.18  4585.9 2014.22  4649.4 2012.07  4706.7 2007.71
  4730.1 2006.87  4771.3 2005.04  4806.7 2001.79  4835.9 2001.29  4856.7 1999.74
    4863 2000.39  4892.1 1999.96  4949.4 1994.32  4956.7 1991.82  4971.3 1989.88
  5029.7 1990.72  5034.7 1989.55  5035.2 1989.05    5065 1989.55  5090.1 2018.38
  5100.2 2024.47  5117.8 2030.87  5122.9  2029.5  5130.4 2032.73  5150.6 2037.79
  5180.8 2041.72  5314.8 2041.79    5320 2041.86  5326.7 2041.94  5402.5 2043.16
#Mann= 7 ,-1 , 0
  4499.4     .07       0  4730.1      .1       0  5034.7     .05       0
    5065      .1       0  5314.8     .07       0    5320      .1       0
  5326.7     .07       0
Bank Sta=5034.7,5065
XS Rating Curve= 0 ,0
Exp/Cntr=0.3,0.1

Type RM Length L Ch R = 1 ,30831   ,528,528,528
BEGIN DESCRIPTION:
Bear Creek 2 53.0
END DESCRIPTION:
XS GIS Cut Line= 3
        1817625.       13943475.        1817425.       13943125.
      1817124.98     13942824.98
#Sta/Elev= 30
  4597.4 2017.54  4670.1 2013.86  4707.5 2009.45    4745 2006.83  4750.7  2007.4
  4758.6 2005.67    4804 2001.17    4902 1996.42  4919.2 1995.88    4971 1993.32
  4977.5 1991.27  4992.6 1990.27  4997.6 1987.31    5004 1987.31  5013.6 1982.58
  5014.1 1982.08  5043.9 1982.58  5071.2 1985.21  5095.1 1994.52  5099.5 1996.37
  5113.6  2020.3  5127.8 2028.32  5141.9 2033.24  5170.2 2039.87  5198.5 2043.44
  5240.9  2044.5  5297.5 2044.81  5361.4 2043.13  5393.7 2042.84  5424.8 2042.85
#Mann= 8 ,-1 , 0
  4597.4     .07       0    4902      .1       0  4919.2     .07       0
  5013.6     .05       0  5043.9     .07       0  5095.1      .1       0
  5361.4     .07       0  5393.7      .1       0
Bank Sta=5013.6,5043.9
XS Rating Curve= 0 ,0
Exp/Cntr=0.3,0.1

Type RM Length L Ch R = 1 ,30303   ,582,582,582
BEGIN DESCRIPTION:
Bear Creek 2 52.0
END DESCRIPTION:
XS GIS Cut Line= 3
        1817925.     13943575.02        1817875.       13943175.
        1818025.     13942374.98
#Sta/Elev= 30
  4597.3 2024.72  4627.6 2024.26  4801.4 2015.45    4882 2004.95  4899.7 2001.44
  4929.9 1992.98  4957.6  1990.1  4990.4 1988.78  4995.4 1987.17  4995.9 1986.67
  5025.8 1987.17  5026.7 1988.69  5086.5 1989.11  5122.5 1988.81  5142.9  1990.1
  5189.5 2001.01  5214.1 2002.87  5242.1 2007.31  5247.2 2006.59  5294.6 2013.05
  5299.7 2012.67  5352.3 2020.86  5357.4 2020.35    5410 2027.36  5437.9 2033.02
  5498.2 2039.65  5580.4 2048.92  5724.5  2061.2  5788.1 2069.52  5814.4 2075.61
#Mann= 6 ,-1 , 0
  4597.3     .07       0  4995.4     .05       0  5025.8     .07       0
  5086.5      .1       0  5498.2     .07       0  5724.5      .1       0
Bank Sta=4995.4,5025.8
XS Rating Curve= 0 ,0
Exp/Cntr=0.3,0.1

Type RM Length L Ch R = 1 ,29721   ,565,565,565
BEGIN DESCRIPTION:
Bear Creek 2 51.0
END DESCRIPTION:
XS GIS Cut Line= 3
        1818425.       13943475.        1818425.       13943075.
        1818475.     13942624.97
#Sta/Elev= 30
  4599.6 2020.03  4639.6 2018.92  4749.6  2013.7  4819.6 2009.32  4849.6  2008.3
  4909.6 2000.84  4919.6 1998.83  4929.6 1995.34  4941.9 1989.43  4949.6 1984.84
  4959.6    1982  4964.4 1978.81  4964.9 1978.31  4994.3 1978.31  4994.8 1978.81
  4997.1 1981.05  5002.1 1981.05  5019.7  1984.1  5039.9 1985.85  5160.6 1992.24
  5210.9 2001.41  5241.1 2006.11  5251.1  2008.6  5281.3 2013.38  5291.4 2016.21
  5301.5 2018.21  5311.5 2019.46  5402.1 2036.69  5422.2 2039.43  5452.4 2042.08
#Mann= 4 ,-1 , 0
  4599.6     .07       0  4941.9      .1       0  4964.4     .05       0
  4994.8      .1       0
Bank Sta=4964.4,4994.8
XS Rating Curve= 0 ,0
Exp/Cntr=0.3,0.1

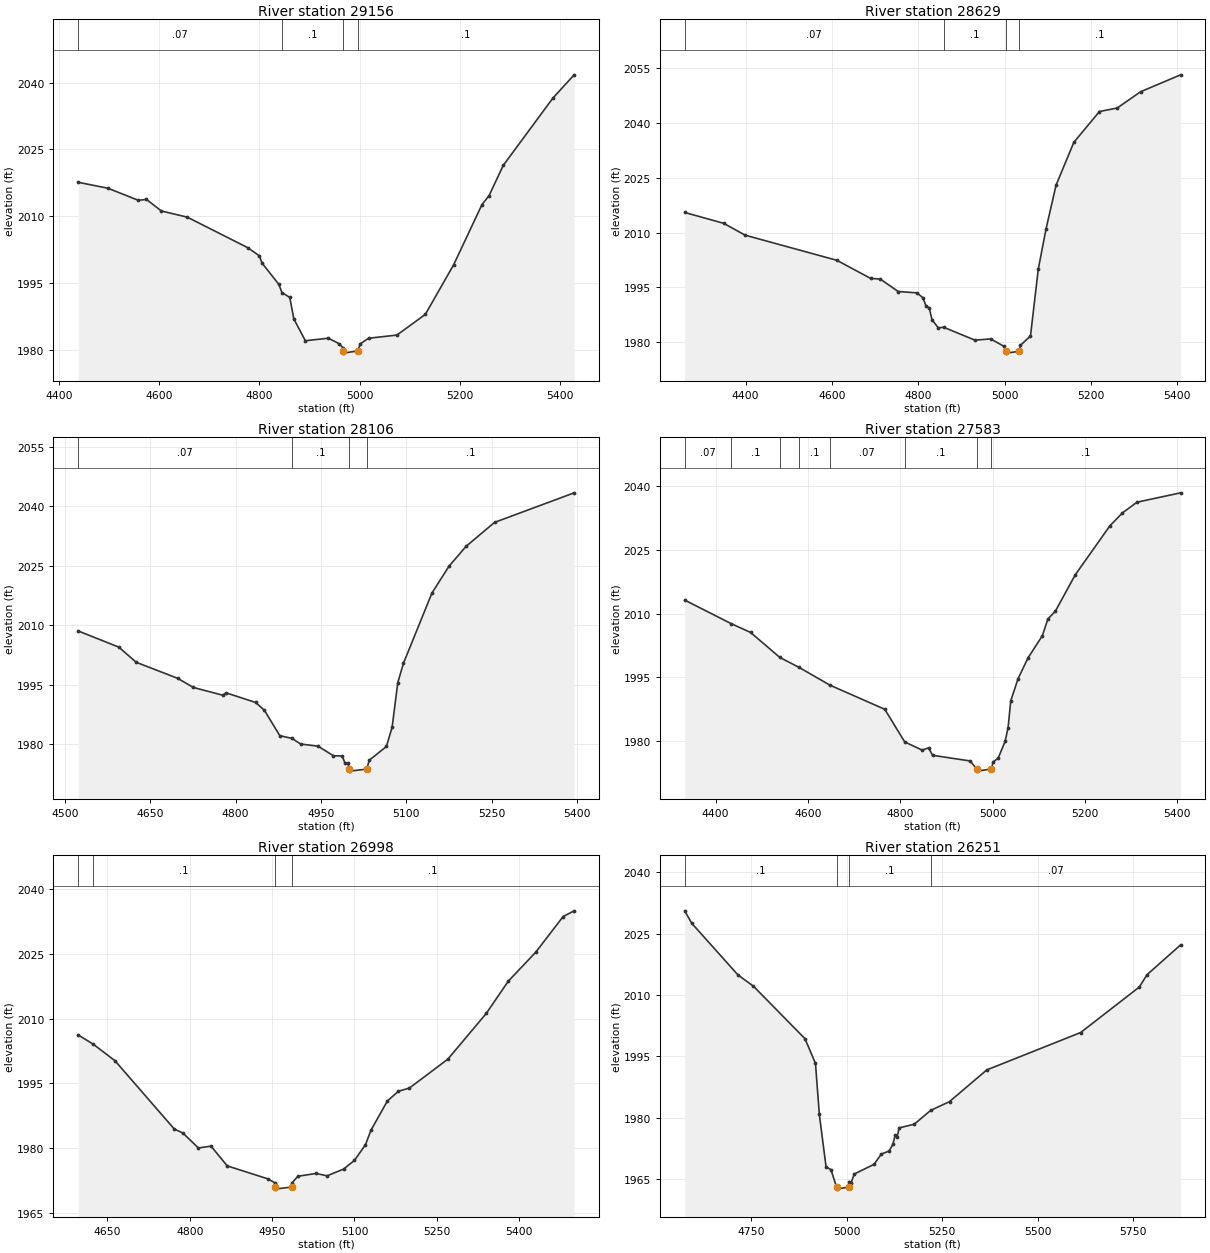
Type RM Length L Ch R = 1 ,29156   ,527,527,527
BEGIN DESCRIPTION:
Bear Creek 2 50.0
END DESCRIPTION:
XS GIS Cut Line= 3
      1818690.03      13943488.8        1818925.       13942975.
      1819224.97     13942675.03
#Sta/Elev= 30
  4438.8 2017.63    4498  2016.3  4558.7 2013.59  4574.9 2013.79  4604.7 2011.19
  4656.3 2009.81  4776.9 2002.96  4799.9 2001.14  4805.8 1999.45  4838.8 1994.75
  4845.2 1992.89  4860.8 1991.78  4868.9 1986.97  4891.9 1982.07  4937.8 1982.64
  4959.8 1981.37  4966.5 1980.54  4966.6 1979.79  4967.1 1979.29    4997 1979.79
    5001 1981.34  5017.9 1982.63  5074.5 1983.34  5131.1 1987.98  5187.6 1999.11
  5244.2 2012.64  5258.3 2014.64  5286.6 2021.43  5385.6 2036.53    5428 2041.75
#Mann= 4 ,-1 , 0
  4438.8     .07       0  4845.2      .1       0  4966.6     .05       0
    4997      .1       0
Bank Sta=4966.6,4997
XS Rating Curve= 0 ,0
Exp/Cntr=0.3,0.1

Type RM Length L Ch R = 1 ,28629   ,523,523,523
BEGIN DESCRIPTION:
Bear Creek 2 49.0
END DESCRIPTION:
XS GIS Cut Line= 3
      1818802.75     13943489.38        1819375.       13943025.
      1819475.01     13942624.98
#Sta/Elev= 30
  4258.8 2015.52  4349.2 2012.55  4398.8 2009.31  4611.4 2002.43  4689.7 1997.48
    4712  1997.3  4753.6 1993.89  4796.8 1993.52  4811.1 1992.18  4817.6 1990.05
  4825.5 1989.39    4832 1986.16  4846.3 1983.98  4859.5 1984.09  4931.4 1980.58
  4967.8 1980.92  4998.3 1978.92  5003.7 1977.53  5004.2 1977.03  5034.2 1977.53
    5037 1979.16  5060.2 1981.74  5078.2 1999.99  5096.3 2011.06  5119.5 2023.01
  5160.7 2034.72    5220 2043.14  5261.2  2044.1  5315.3 2048.55  5408.1 2053.18
#Mann= 4 ,-1 , 0
  4258.8     .07       0  4859.5      .1       0  5003.7     .05       0
  5034.2      .1       0
Bank Sta=5003.7,5034.2
XS Rating Curve= 0 ,0
Exp/Cntr=0.3,0.1

Type RM Length L Ch R = 1 ,28106   ,523,523,523
BEGIN DESCRIPTION:
Bear Creek 2 48.0
END DESCRIPTION:
XS GIS Cut Line= 3
      1819574.99     13943625.02        1819825.       13943225.
        1819825.     13942825.02
#Sta/Elev= 30
  4523.5  2008.6  4594.9 2004.52  4625.5  2000.7  4698.6 1996.64  4725.8 1994.36
  4777.7  1992.4  4783.5    1993  4835.4 1990.57  4850.8 1988.59  4877.9 1982.19
  4899.2 1981.52  4914.4  1980.1  4945.1 1979.54  4972.2 1977.13  4987.6 1977.08
  4992.3 1975.31  4997.7 1975.31  4999.9 1973.76  5000.4 1973.26  5030.5 1973.76
  5035.2 1976.02  5065.2 1979.47  5075.2 1984.29  5085.2 1995.57  5095.2 2000.46
  5145.2 2018.15  5175.2 2024.92  5205.2 2029.93  5255.2 2035.97  5395.2 2043.43
#Mann= 4 ,-1 , 0
  4523.5     .07       0  4899.2      .1       0  4999.9     .05       0
  5030.5      .1       0
Bank Sta=4999.9,5030.5
XS Rating Curve= 0 ,0
Exp/Cntr=0.3,0.1

Type RM Length L Ch R = 1 ,27583   ,585,585,585
BEGIN DESCRIPTION:
Bear Creek 2 47.0
END DESCRIPTION:
XS GIS Cut Line= 3
      1819974.99     13944025.02        1820275.       13943425.
      1820625.04     13943224.98
#Sta/Elev= 30
  4333.1  2013.2    4434 2007.64  4475.7 2005.59  4539.3 1999.69  4580.3 1997.39
  4647.5 1993.19  4766.4  1987.5  4809.6 1979.82  4847.4 1977.89  4861.4 1978.44
  4869.8 1976.68  4950.8 1975.35  4966.2 1973.45  4966.7 1972.95  4996.9 1973.45
  5001.1 1975.11  5011.9 1975.99    5027 1979.93  5033.5 1983.19  5039.2 1989.48
    5055 1994.68  5076.6 1999.59  5107.6 2004.79  5119.8 2008.79  5135.7 2010.55
  5178.9 2019.14  5253.7 2030.63  5281.1 2033.71  5312.8 2036.23  5407.1 2038.43
#Mann= 8 ,-1 , 0
  4333.1     .07       0    4434      .1       0  4539.3     .07       0
  4580.3      .1       0  4647.5     .07       0  4809.6      .1       0
  4966.2     .05       0  4996.9      .1       0
Bank Sta=4966.2,4996.9
XS Rating Curve= 0 ,0
Exp/Cntr=0.3,0.1

Type RM Length L Ch R = 1 ,26998   ,747,747,747
BEGIN DESCRIPTION:
Bear Creek 2 46.0
END DESCRIPTION:
XS GIS Cut Line= 3
      1820475.02     13944174.96        1820675.       13943825.
        1820675.     13943324.97
#Sta/Elev= 30
  4596.9 2006.22  4624.6 2004.04  4663.8 2000.24  4771.8 1984.39  4787.6 1983.44
  4815.7 1979.99  4838.7 1980.41  4868.2 1975.83  4942.4 1972.81  4954.6 1971.92
  4955.1 1970.93  4955.6 1970.43  4985.8 1970.93  4986.3  1971.9  4997.1 1973.42
    5030 1974.07    5050 1973.52    5080 1975.07    5100 1977.11    5120 1980.74
    5130  1984.1    5160 1990.91    5180 1993.15    5200 1993.89    5270  2000.6
    5340 2011.22    5380 2018.69    5430 2025.42    5480 2033.71    5500 2035.03
#Mann= 4 ,-1 , 0
  4596.9     .07       0  4624.6      .1       0  4955.1     .05       0
  4985.8      .1       0
Bank Sta=4955.1,4985.8
XS Rating Curve= 0 ,0
Exp/Cntr=0.3,0.1

Type RM Length L Ch R = 1 ,26251   ,400,400,400
BEGIN DESCRIPTION:
Bear Creek 2 45.1
END DESCRIPTION:
XS GIS Cut Line= 3
      1821312.32     13944642.64      1821218.11     13944087.26
      1821059.02     13943369.29
#Sta/Elev= 30
  4575.9 2030.59  4594.3 2027.56  4715.5 2014.91  4756.1 2012.15  4890.9 1999.33
  4918.4  1993.3  4928.5 1980.82  4946.1 1968.01  4958.9 1967.31  4973.7 1963.05
  4974.2 1962.55    5005 1963.05  5006.5  1964.4  5011.5 1964.01  5019.8 1966.23
  5071.9 1968.62  5090.8 1971.11  5111.1 1971.87  5121.2 1973.49  5127.1 1975.77
  5132.2 1975.34  5137.8 1977.53    5177 1978.42    5220 1981.79  5269.4 1983.95
  5366.9 1991.69  5612.7 2000.83  5766.3 2011.95  5786.8 2014.99  5874.6 2022.27
#Mann= 4 ,-1 , 0
  4575.9      .1       0  4973.7     .05       0    5005      .1       0
    5220     .07       0
Bank Sta=4973.7,5005
XS Rating Curve= 0 ,0
Exp/Cntr=0.3,0.1

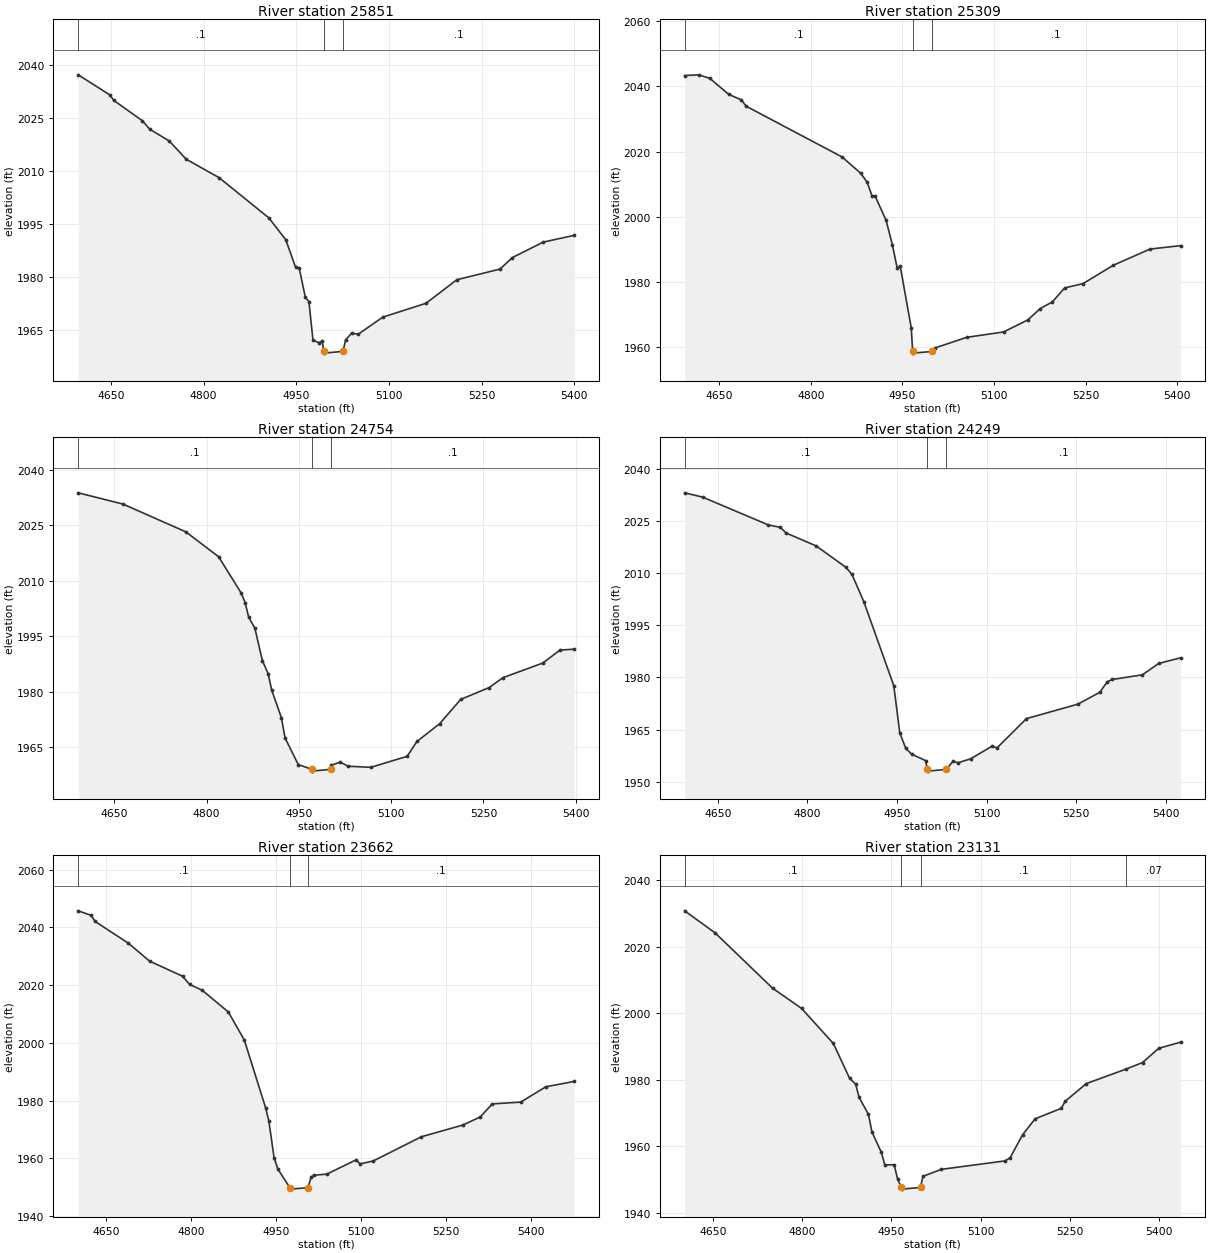
Type RM Length L Ch R = 1 ,25851   ,542,542,542
BEGIN DESCRIPTION:
Bear Creek 2 45.0
END DESCRIPTION:
XS GIS Cut Line= 3
        1821825.       13944625.        1821625.       13944275.
        1821625.     13943875.01
#Sta/Elev= 30
  4596.9 2037.32    4648 2031.65  4654.5 2030.08  4700.6 2024.35  4712.8 2021.92
  4744.5 2018.58  4771.8 2013.43  4825.1 2008.21  4905.7 1996.81  4933.1 1990.62
  4948.9 1982.82  4954.7 1982.68  4964.7 1974.35  4970.5 1973.13    4977 1962.29
  4986.3 1961.49  4992.1 1961.94  4994.4 1959.05  4994.9 1958.55  5025.7 1959.05
    5030 1962.36    5040 1964.24    5050 1963.85    5090 1968.73    5160 1972.65
    5210 1979.32    5280 1982.34    5300  1985.6    5350 1989.98    5400 1991.88
#Mann= 3 ,-1 , 0
  4596.9      .1       0  4994.4     .05       0  5025.7      .1       0
Bank Sta=4994.4,5025.7
XS Rating Curve= 0 ,0
Exp/Cntr=0.3,0.1

Type RM Length L Ch R = 1 ,25309   ,555,555,555
BEGIN DESCRIPTION:
Bear Creek 2 44.0
END DESCRIPTION:
XS GIS Cut Line= 3
      1822024.99     13944625.03        1822125.       13944225.
        1822125.     13943825.04
#Sta/Elev= 30
  4593.3 2043.33  4616.5 2043.55  4634.6 2042.45  4665.5 2037.54  4686.1 2035.88
  4693.8 2033.94    4851 2018.36  4881.9 2013.29  4892.3 2010.56    4900 2006.44
  4905.1 2006.41  4923.2  1998.9  4933.5 1991.41  4941.2  1984.4  4946.4 1984.81
  4964.4 1965.92  4966.7 1958.66  4967.2 1958.16  4998.1 1958.66  5003.1 1959.74
  5055.6 1963.02  5115.6 1964.65  5155.6 1968.38  5175.6 1971.83  5195.6 1973.88
  5215.6 1978.17  5245.6 1979.48  5295.6 1985.14  5355.6 1990.09  5405.6 1991.14
#Mann= 3 ,-1 , 0
  4593.3      .1       0  4966.7     .05       0  4998.1      .1       0
Bank Sta=4966.7,4998.1
XS Rating Curve= 0 ,0
Exp/Cntr=0.3,0.1

Type RM Length L Ch R = 1 ,24754   ,505,505,505
BEGIN DESCRIPTION:
Bear Creek 2 43.0
END DESCRIPTION:
XS GIS Cut Line= 3
      1822974.97     13944274.99        1822625.       13944075.
        1822425.       13943725.
#Sta/Elev= 30
  4591.3 2033.72    4664 2030.68  4766.2 2023.18  4819.5 2016.45  4856.2 2006.65
  4862.7 2004.03  4868.4 2000.13  4878.5 1997.09  4890.7 1988.36  4900.1 1984.81
  4905.8 1980.39  4921.7 1972.89  4927.4  1967.5    4949 1960.28  4970.7 1958.99
  4971.2 1958.49  5002.2 1958.99  5002.3 1960.05  5017.4 1960.94  5029.7 1959.82
  5067.1 1959.52  5126.1  1962.5    5142 1966.52  5178.7 1971.29  5213.2 1977.89
  5259.3 1981.07  5281.6 1983.74  5346.4  1987.7  5374.5  1991.2  5397.5 1991.46
#Mann= 3 ,-1 , 0
  4591.3      .1       0  4970.7     .05       0  5002.2      .1       0
Bank Sta=4970.7,5002.2
XS Rating Curve= 0 ,0
Exp/Cntr=0.3,0.1

Type RM Length L Ch R = 1 ,24249   ,587,587,587
BEGIN DESCRIPTION:
Bear Creek 2 42.0
END DESCRIPTION:
XS GIS Cut Line= 3
        1823025.     13944225.02        1823025.       13943825.
      1822675.03     13943575.02
#Sta/Elev= 30
  4594.7 2033.18  4624.7 2031.95  4734.7 2023.93  4754.7 2023.24  4764.7 2021.59
  4814.7 2017.89  4864.7 2011.71  4874.7 2009.68  4894.7 2001.76  4944.7 1977.63
  4954.7 1964.04  4964.7 1959.58  4974.7 1957.88  4997.8 1956.06  5001.1 1953.51
  5001.6 1953.01  5032.6 1953.51  5043.9 1955.85  5052.5 1955.43  5073.4 1956.56
    5109 1960.18  5117.6 1959.72  5166.8 1968.14  5252.8  1972.3  5289.7 1975.73
  5301.9 1978.74  5310.5 1979.41  5360.9 1980.76    5388 1984.02  5424.8 1985.66
#Mann= 3 ,-1 , 0
  4594.7      .1       0  5001.1     .05       0  5032.6      .1       0
Bank Sta=5001.1,5032.6
XS Rating Curve= 0 ,0
Exp/Cntr=0.3,0.1

Type RM Length L Ch R = 1 ,23662   ,531,531,531
BEGIN DESCRIPTION:
Bear Creek 2 41.0
END DESCRIPTION:
XS GIS Cut Line= 3
        1823725.       13943575.        1823375.       13943375.
      1822975.01     13943125.01
#Sta/Elev= 30
  4601.5 2045.71  4624.5 2044.12    4631 2042.07    4690 2034.51  4727.5 2028.28
  4785.8 2023.06    4798 2020.22  4820.3 2018.22  4866.4 2010.67  4894.5 2000.99
  4931.9 1977.63  4937.7 1973.04    4947  1960.3  4953.5 1956.39  4974.9 1949.89
  4975.4 1949.39    5007 1949.89  5012.3  1953.6  5018.2 1954.22    5040 1954.58
  5091.3 1959.49    5099 1958.13  5121.9 1959.13  5206.9 1967.52    5280 1971.57
  5310.6 1974.37  5331.9 1978.89    5382  1979.5  5426.2  1984.8  5476.3 1986.67
#Mann= 3 ,-1 , 0
  4601.5      .1       0  4974.9     .05       0    5007      .1       0
Bank Sta=4974.9,5007
XS Rating Curve= 0 ,0
Exp/Cntr=0.3,0.1

Type RM Length L Ch R = 1 ,23131   ,505,505,505
BEGIN DESCRIPTION:
Bear Creek 2 40.0
END DESCRIPTION:
XS GIS Cut Line= 3
        1823825.       13943275.        1823625.       13942925.
      1823375.01     13942575.02
#Sta/Elev= 30
  4602.9 2030.77    4654 2024.15  4750.5 2007.55  4799.4 2001.44  4852.7 1990.93
    4880 1980.47  4890.1 1978.71  4895.9 1974.78  4911.7  1969.6  4917.5 1964.36
  4933.3 1958.23  4939.1  1954.5  4954.9 1954.48  4960.7 1950.18  4966.8 1947.68
  4967.4 1947.18  4999.1 1947.68  5003.1 1951.02  5034.3 1953.13  5141.2 1955.66
  5149.8 1956.65  5170.7 1963.53  5191.6 1968.29  5235.8 1971.46    5242 1973.54
  5277.6 1978.87  5345.1 1983.28  5372.2 1985.21  5399.3 1989.48  5436.1 1991.32
#Mann= 4 ,-1 , 0
  4602.9      .1       0  4966.8     .05       0  4999.1      .1       0
  5345.1     .07       0
Bank Sta=4966.8,4999.1
XS Rating Curve= 0 ,0
Exp/Cntr=0.3,0.1

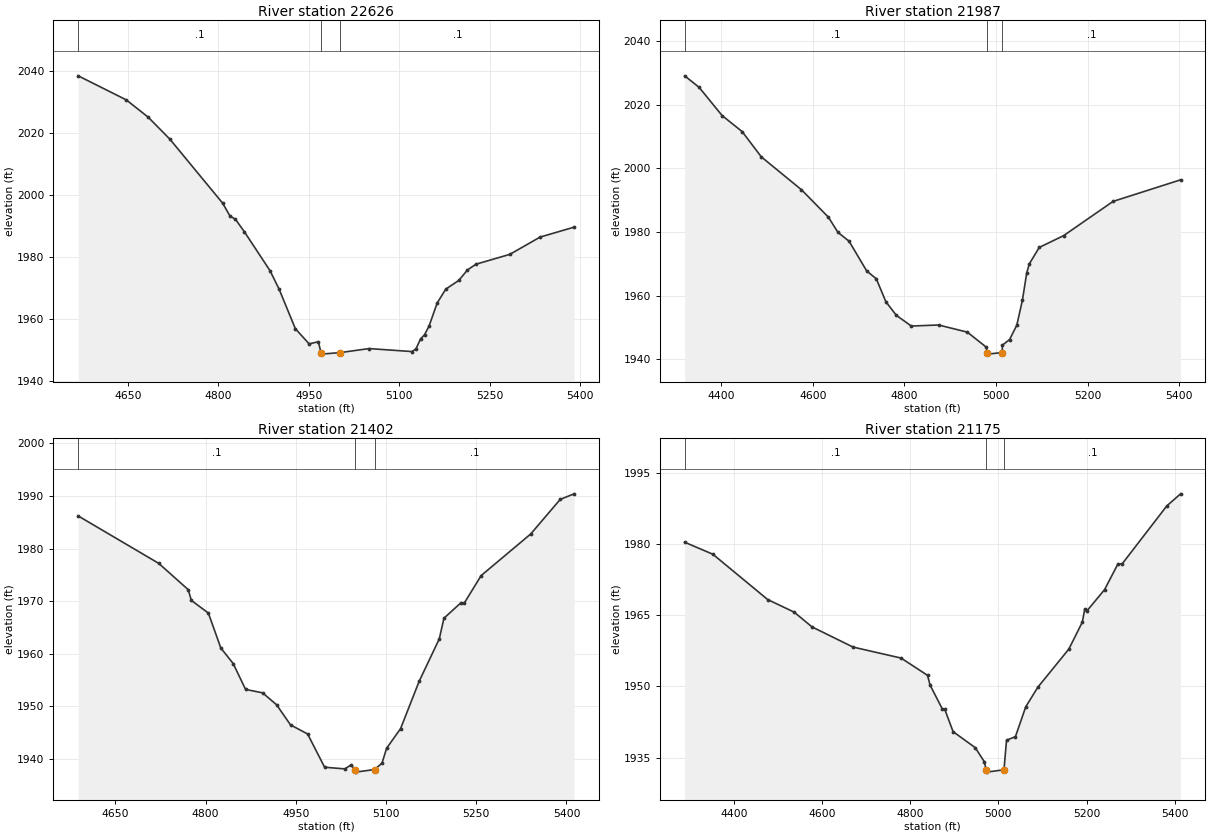
Type RM Length L Ch R = 1 ,22626   ,639,639,639
BEGIN DESCRIPTION:
Bear Creek 2 39.0
END DESCRIPTION:
XS GIS Cut Line= 3
      1824274.98     13942774.99      1823944.96     13942558.22
      1823624.96     13942274.97
#Sta/Elev= 30
  4567.7 2038.36  4647.5  2030.6  4683.7 2025.04  4719.9  2017.9    4807 1997.37
  4819.2 1993.23  4828.4 1992.13  4842.9 1988.19  4885.6 1975.61  4900.7 1969.65
  4927.7 1956.88  4950.5    1952  4965.9 1952.68  4970.1 1949.19  4970.6 1948.69
  5002.4 1949.19  5049.8 1950.48  5120.9 1949.52  5127.6 1950.37  5135.2 1953.58
  5141.8 1954.92  5149.4 1957.75  5162.8 1965.16    5177 1969.62  5198.7 1972.45
    5213 1975.81  5227.2 1977.67  5283.2 1980.83  5333.4  1986.4  5389.9 1989.61
#Mann= 3 ,-1 , 0
  4567.7      .1       0  4970.1     .05       0  5002.4      .1       0
Bank Sta=4970.1,5002.4
XS Rating Curve= 0 ,0
Exp/Cntr=0.3,0.1

Type RM Length L Ch R = 1 ,21987   ,585,585,585
BEGIN DESCRIPTION:
Bear Creek 2 38.0
END DESCRIPTION:
XS GIS Cut Line= 3
      1824375.01     13942675.02        1824175.       13942025.
        1823975.     13941675.01
#Sta/Elev= 30
  4319.9 2029.14  4351.3 2025.54  4401.7 2016.64  4445.5  2011.6  4487.3 2003.65
    4575 1993.32  4633.8  1984.7  4654.7 1979.91  4678.9 1977.15  4717.5 1967.78
  4738.4 1965.33  4759.4 1958.09  4782.2 1953.83  4814.9 1950.46  4874.4 1950.79
  4937.2 1948.55  4978.4 1943.85  4981.2 1942.13  4981.7 1941.63  5013.6 1942.13
  5013.7 1944.43  5029.5 1946.21  5045.3 1950.73  5057.6  1958.6  5066.9 1967.11
  5072.7 1970.02  5094.3 1975.18  5147.6 1978.89  5255.5 1989.65  5403.1 1996.44
#Mann= 3 ,-1 , 0
  4319.9      .1       0  4981.2     .05       0  5013.6      .1       0
Bank Sta=4981.2,5013.6
XS Rating Curve= 0 ,0
Exp/Cntr=0.3,0.1

Type RM Length L Ch R = 1 ,21402   ,227,227,227
BEGIN DESCRIPTION:
Bear Creek 2 37.0
END DESCRIPTION:
XS GIS Cut Line= 3
      1824674.99     13942024.97        1824575.       13941625.
      1824174.99       13941525.
#Sta/Elev= 30
  4588.2 1986.21  4722.2 1977.18  4771.1 1972.18  4776.3 1970.14  4804.6 1967.73
  4825.3 1961.09  4845.9 1958.11  4866.5  1953.2  4894.8 1952.55    4918 1950.28
  4941.2 1946.45  4969.6 1944.72  4997.9 1938.39  5031.4 1938.08  5041.7 1938.81
  5048.7 1937.96  5049.3 1937.46  5081.1 1937.96  5093.3 1939.17    5101 1942.01
  5124.2 1945.74  5155.1 1954.75  5188.6 1962.83  5196.3 1966.75  5224.7  1969.7
  5229.8 1969.57  5258.2 1974.87  5340.6 1982.78  5389.6 1989.36  5412.8 1990.42
#Mann= 3 ,-1 , 0
  4588.2      .1       0  5048.7     .05       0  5081.1      .1       0
Bank Sta=5048.7,5081.1
XS Rating Curve= 0 ,0
Exp/Cntr=0.3,0.1

Type RM Length L Ch R = 1 ,21175   ,838,838,838
BEGIN DESCRIPTION:
Bear Creek 2 36.1
END DESCRIPTION:
XS GIS Cut Line= 3
      1825304.68     13941648.18      1824757.86     13941437.27
      1824224.17     13941358.19
#Sta/Elev= 30
  4287.9 1980.36  4351.9 1977.83  4476.2 1968.29  4536.2 1965.64  4576.9 1962.52
    4670 1958.27  4779.1 1955.95  4839.1 1952.31  4844.9 1950.25  4872.8  1945.2
    4878  1945.2  4897.1 1940.45  4947.6 1937.06  4967.9 1934.12  4972.3 1932.42
  4973.3 1931.92  5012.6 1932.42  5018.4 1938.64  5038.6  1939.4    5062 1945.68
  5089.2 1949.78  5159.9 1957.86  5190.3  1963.5  5195.9 1966.24    5201 1965.91
  5240.8 1970.36  5271.1 1975.76  5281.2 1975.85  5382.3 1988.03  5413.5 1990.56
#Mann= 3 ,-1 , 0
  4287.9      .1       0  4972.3     .05       0  5012.6      .1       0
Bank Sta=4972.3,5012.6
XS Rating Curve= 0 ,0
Exp/Cntr=0.3,0.1