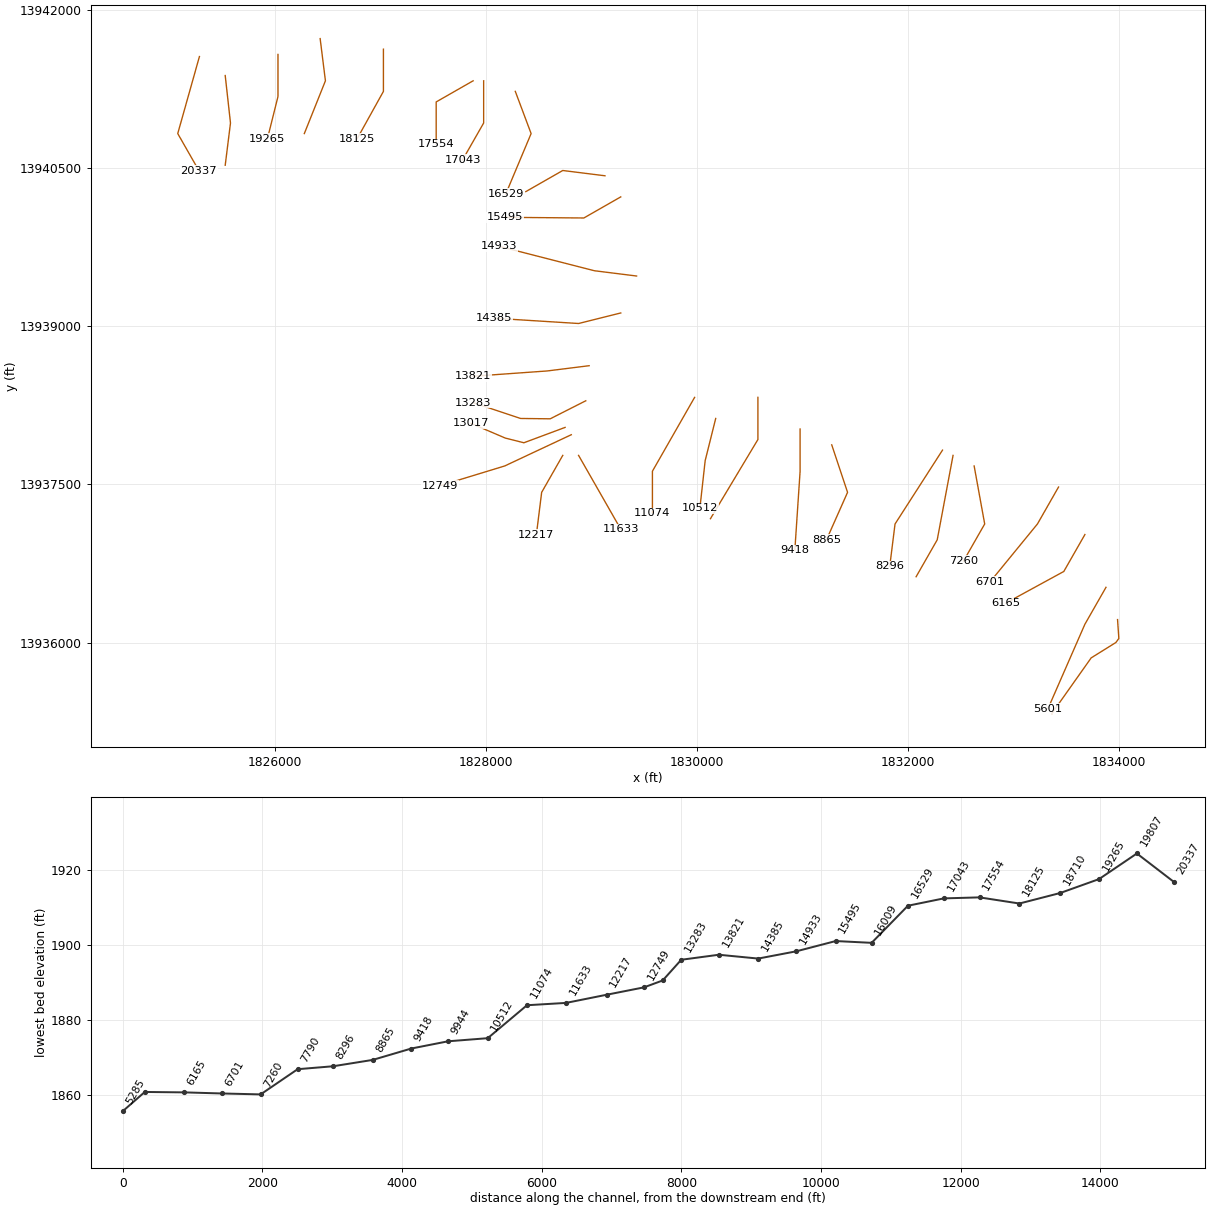
HEC-RAS study Bear Creek 2.prj: Bear Creek 2 Base Level Engineering

--- Bear Creek 2.g01 (geometry) --- (continued)

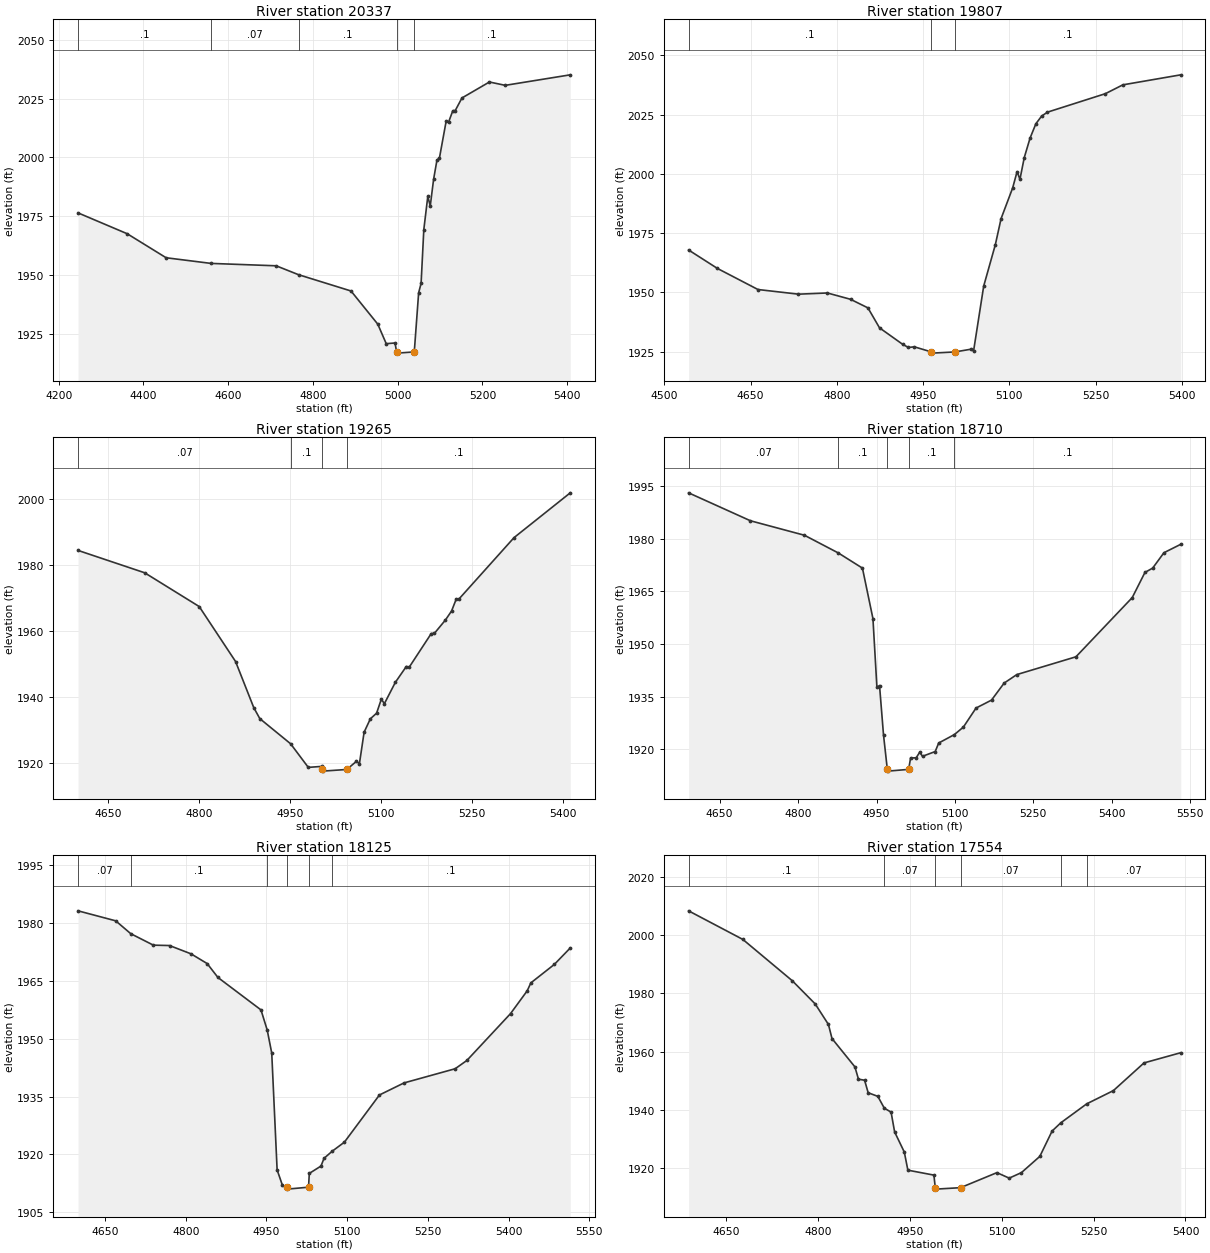
Type RM Length L Ch R = 1 ,20337   ,530,530,530
BEGIN DESCRIPTION:
Bear Creek 2 36.0
END DESCRIPTION:
XS GIS Cut Line= 3
      1825280.54     13941555.07        1825075.       13940825.
      1825275.02     13940474.97
#Sta/Elev= 30
  4245.7 1976.43  4361.8 1967.56  4453.6 1957.35  4559.5 1954.95  4713.3 1953.93
    4766 1950.15  4889.9 1943.22  4953.1 1929.11    4973 1920.82  4993.8 1921.11
  4997.5  1917.3  4998.5  1916.8  5038.2  1917.3  5039.4  1917.8  5049.5 1942.46
  5055.3 1946.47  5061.7 1969.31  5071.1 1983.45  5076.9 1979.38  5084.8  1990.7
  5092.7 1998.85  5098.5 1999.68  5114.3  2015.3    5120 2014.95  5130.1 2019.85
  5135.9 2019.95  5151.7 2025.29  5216.5 2032.08  5253.9 2030.66  5407.3 2035.13
#Mann= 5 ,-1 , 0
  4245.7      .1       0  4559.5     .07       0    4766      .1       0
  4997.5     .05       0  5038.2      .1       0
Bank Sta=4997.5,5038.2
XS Rating Curve= 0 ,0
Exp/Cntr=0.3,0.1

Type RM Length L Ch R = 1 ,19807   ,542,542,542
BEGIN DESCRIPTION:
Bear Creek 2 35.0
END DESCRIPTION:
XS GIS Cut Line= 3
        1825525.     13941374.97        1825575.       13940925.
      1825524.99     13940524.95
#Sta/Elev= 30
  4542.3 1967.92  4592.6 1960.11    4663 1951.23  4733.4 1949.27  4783.7 1949.77
    4824  1947.1  4854.2 1943.48  4874.3 1935.07  4914.5 1928.12  4924.6 1926.77
  4934.7 1927.06  4964.6 1924.89  4965.6 1924.39  5005.4 1924.89  5032.8 1926.02
  5037.9 1925.33  5055.5 1952.71  5075.7 1970.14  5085.7 1981.15  5105.9 1994.15
  5113.5 2000.98  5118.5 1997.75    5126  2006.9  5136.1 2015.13  5146.2 2021.18
  5156.3 2024.45  5166.4 2026.08  5267.1 2033.88  5297.4  2037.6  5398.2 2041.83
#Mann= 3 ,-1 , 0
  4542.3      .1       0  4964.6     .05       0  5005.4      .1       0
Bank Sta=4964.6,5005.4
XS Rating Curve= 0 ,0
Exp/Cntr=0.3,0.1

Type RM Length L Ch R = 1 ,19265   ,555,555,555
BEGIN DESCRIPTION:
Bear Creek 2 34.0
END DESCRIPTION:
XS GIS Cut Line= 3
        1826025.     13941574.95        1826025.       13941175.
      1825924.99     13940774.97
#Sta/Elev= 30
  4600.2 1984.35  4710.2 1977.58  4800.2 1967.36  4860.2 1950.72  4890.2 1936.77
  4900.2 1933.44    4951 1925.83  4980.2 1918.68  5002.7 1918.99  5002.9 1918.05
  5003.9 1917.55  5043.7 1918.05  5059.4 1920.48  5064.6 1919.84  5072.3 1929.33
  5082.6 1933.38  5092.9 1935.09  5100.7 1939.31  5105.8 1937.98  5123.8 1944.41
  5141.9 1949.21    5147 1949.09  5183.1 1959.19  5188.3 1959.25  5206.3 1963.24
  5216.6    1966  5224.3 1969.61  5229.5 1969.78  5319.7 1988.22  5412.5 2001.78
#Mann= 4 ,-1 , 0
  4600.2     .07       0    4951      .1       0  5002.9     .05       0
  5043.7      .1       0
Bank Sta=5002.9,5043.7
XS Rating Curve= 0 ,0
Exp/Cntr=0.3,0.1

Type RM Length L Ch R = 1 ,18710   ,585,585,585
BEGIN DESCRIPTION:
Bear Creek 2 33.0
END DESCRIPTION:
XS GIS Cut Line= 3
        1826425.       13941725.        1826475.       13941325.
      1826275.01     13940825.03
#Sta/Elev= 30
  4590.5    1993  4708.9 1985.05  4812.2 1980.93  4876.9  1975.9  4923.1 1971.58
  4943.2 1957.22  4950.8 1937.63  4955.8 1938.19  4963.4 1924.14  4970.7 1914.34
  4971.7 1913.84  5011.5 1914.34  5015.2 1917.58  5025.9 1917.63  5032.7 1919.23
    5038 1918.06  5062.3 1919.41    5069 1921.84  5098.9 1924.23  5116.1 1926.35
  5140.4 1931.78    5170 1934.04  5194.2 1938.89  5218.4  1941.3  5331.5 1946.36
  5439.2  1963.2  5463.5 1970.36  5478.3 1971.59  5499.8 1975.96  5532.1 1978.37
#Mann= 5 ,-1 , 0
  4590.5     .07       0  4876.9      .1       0  4970.7     .05       0
  5011.5      .1       0  5098.9      .1       0
Bank Sta=4970.7,5011.5
XS Rating Curve= 0 ,0
Exp/Cntr=0.3,0.1

Type RM Length L Ch R = 1 ,18125   ,571,571,571
BEGIN DESCRIPTION:
Bear Creek 2 32.0
END DESCRIPTION:
XS GIS Cut Line= 3
        1827025.     13941625.03        1827025.       13941225.
      1826775.01     13940775.01
#Sta/Elev= 30
  4599.9 1983.11  4669.9 1980.52  4697.9 1977.19  4739.9 1974.22  4769.9 1974.12
  4809.9 1971.97  4839.9 1969.45  4859.9 1965.85  4939.9 1957.45  4951.5 1952.23
  4959.9 1946.27  4969.9 1916.02  4979.9 1911.97  4987.5 1911.53  4988.5 1911.03
  5028.3 1911.53  5029.7  1915.1  5051.4    1917  5057.1 1919.01  5072.2 1920.84
  5094.9 1923.19  5160.1 1935.42  5205.8 1938.54  5300.8 1942.21  5322.5 1944.35
  5403.7 1956.49  5434.6 1962.38  5441.5 1964.45    5485 1969.22  5514.7 1973.49
#Mann= 6 ,-1 , 0
  4599.9     .07       0  4697.9      .1       0  4951.5     .07       0
  4987.5     .05       0  5028.3     .07       0  5072.2      .1       0
Bank Sta=4987.5,5028.3
XS Rating Curve= 0 ,0
Exp/Cntr=0.3,0.1

Type RM Length L Ch R = 1 ,17554   ,511,511,511
BEGIN DESCRIPTION:
Bear Creek 2 31.0
END DESCRIPTION:
XS GIS Cut Line= 3
      1827875.02     13941325.01        1827525.       13941125.
        1827525.     13940725.04
#Sta/Elev= 30
  4589.3 2008.38  4677.9 1998.54  4758.5 1984.34  4795.9 1976.36  4817.5  1969.3
  4823.3 1964.46  4860.7 1954.71  4866.5 1950.48  4876.5 1950.12  4882.3 1945.82
  4898.1 1944.57  4908.7 1940.49  4919.7 1939.16  4925.5 1932.34  4941.3 1925.41
  4947.1 1919.19  4989.6 1917.49  4991.8 1913.17  4992.8 1912.67    5033 1913.17
  5092.4 1918.34  5112.4 1916.45  5132.4 1918.35  5162.4 1923.93  5182.4 1932.64
  5196.7 1935.49  5238.9    1942  5282.4 1946.55  5332.4 1956.08  5392.4 1959.59
#Mann= 6 ,-1 , 0
  4589.3      .1       0  4908.7     .07       0  4991.8     .05       0
    5033     .07       0  5196.7      .1       0  5238.9     .07       0
Bank Sta=4991.8,5033
XS Rating Curve= 0 ,0
Exp/Cntr=0.3,0.1

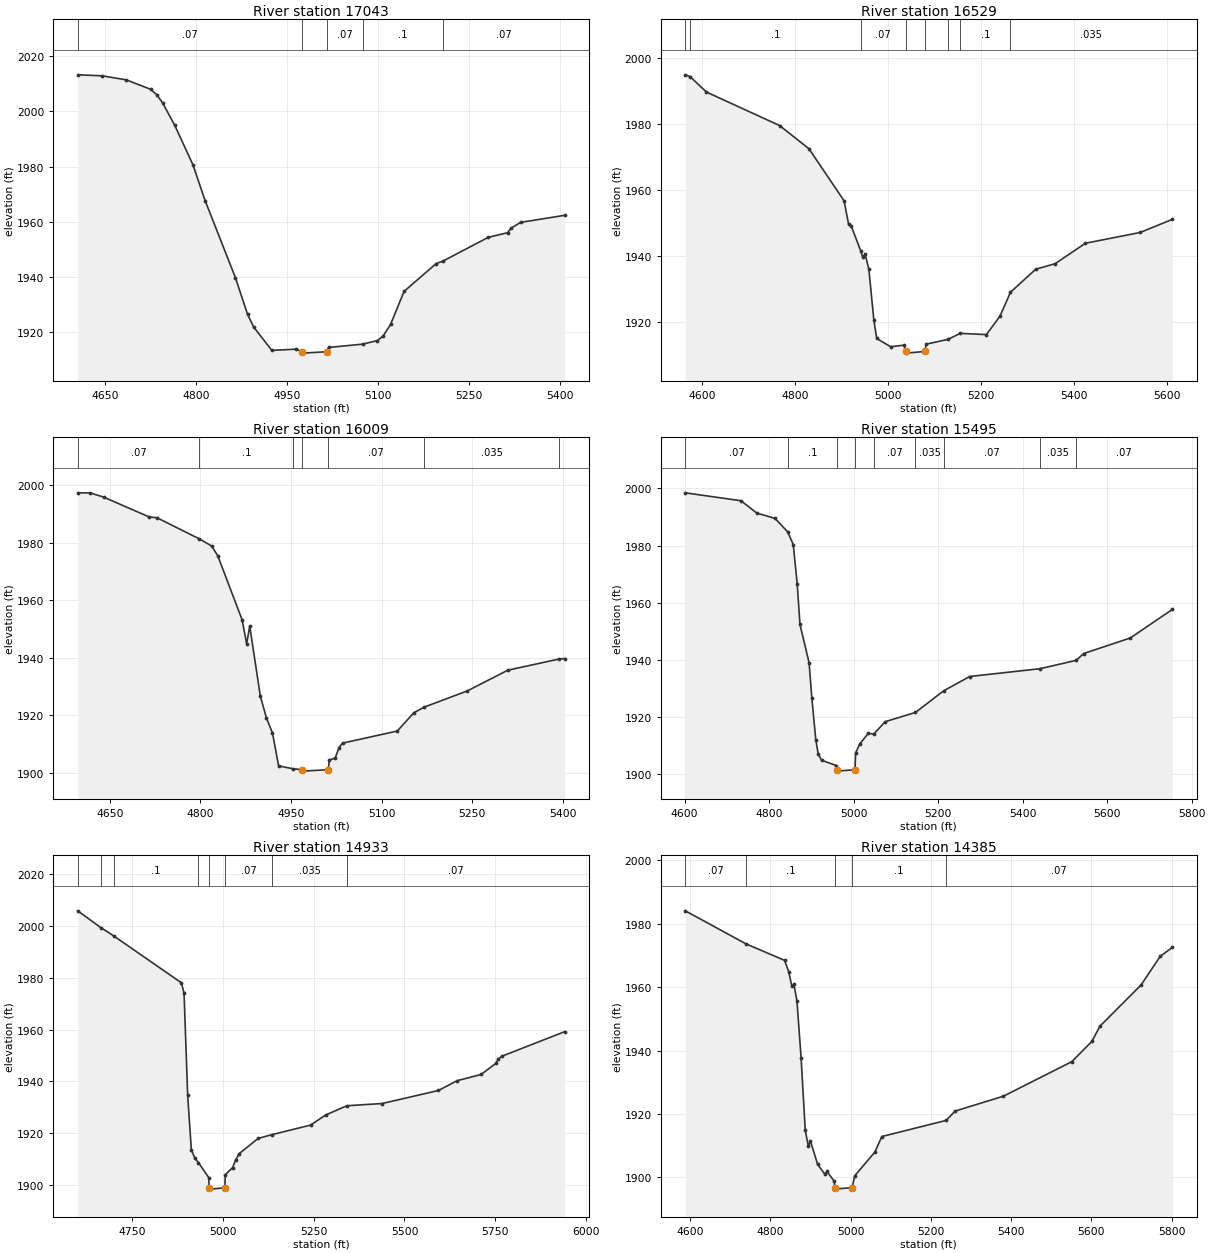
Type RM Length L Ch R = 1 ,17043   ,514,514,514
BEGIN DESCRIPTION:
Bear Creek 2 30.0
END DESCRIPTION:
XS GIS Cut Line= 3
        1827975.     13941325.01        1827975.       13940925.
      1827775.01     13940575.02
#Sta/Elev= 30
  4604.6 2013.24  4644.6 2012.89  4684.6 2011.42  4724.6 2008.01  4734.6 2006.09
  4744.6 2003.06  4764.6 1994.92  4794.6 1980.62  4814.6 1967.66  4864.6 1939.76
  4884.6 1926.46  4894.6  1921.9  4924.6  1913.4  4964.6 1913.83    4974  1912.9
    4975  1912.4  5015.2  1912.9  5018.3 1914.46  5074.7 1915.66  5098.9 1916.97
  5108.3 1918.64  5120.5 1922.81  5142.8 1934.78  5195.4 1944.79  5206.9 1945.76
  5281.8 1954.37  5313.4 1956.03  5319.2 1957.67    5335 1959.78  5407.7 1962.34
#Mann= 5 ,-1 , 0
  4604.6     .07       0    4974     .05       0  5015.2     .07       0
  5074.7      .1       0  5206.9     .07       0
Bank Sta=4974,5015.2
XS Rating Curve= 0 ,0
Exp/Cntr=0.3,0.1

Type RM Length L Ch R = 1 ,16529   ,520,520,520
BEGIN DESCRIPTION:
Bear Creek 2 29.0
END DESCRIPTION:
XS GIS Cut Line= 3
      1828275.01     13941224.97        1828425.       13940825.
      1828184.66     13940252.58
#Sta/Elev= 30
    4564 1994.92  4574.2 1994.39  4609.4  1989.7  4766.9 1979.52  4830.1 1972.48
  4905.7 1956.68  4915.5 1949.49  4920.9  1949.1  4941.3 1941.56  4945.8 1939.55
  4951.1 1940.48  4959.1 1935.84  4969.8 1920.42    4976 1914.89  5005.8 1912.38
  5034.9 1912.86  5038.1 1910.94  5039.1 1910.44  5079.4 1910.94  5082.5 1913.17
  5129.3 1914.61  5155.7 1916.44  5212.1 1916.07  5241.3 1921.69  5263.8 1928.92
    5318 1935.89  5359.9 1937.59    5425 1943.79  5542.7 1947.06    5612 1951.04
#Mann= 8 ,-1 , 0
    4564     .07       0  4574.2      .1       0  4941.3     .07       0
  5038.1     .05       0  5079.4     .07       0  5129.3     .07       0
  5155.7      .1       0  5263.8    .035       0
Bank Sta=5038.1,5079.4
XS Rating Curve= 0 ,0
Exp/Cntr=0.3,0.1

Type RM Length L Ch R = 1 ,16009   ,514,514,514
BEGIN DESCRIPTION:
Bear Creek 2 28.0
END DESCRIPTION:
XS GIS Cut Line= 3
      1829124.96     13940425.01        1828725.       13940475.
      1828374.99     13940274.99
#Sta/Elev= 30
  4596.9 1997.28    4617 1997.26  4639.7 1995.79  4715.3 1988.88  4727.9 1988.63
  4798.4 1981.25  4818.6 1978.79  4828.6 1975.44    4869 1953.13  4876.5  1944.8
  4881.6 1950.94  4899.2 1926.56  4909.3 1918.99  4919.3 1913.78  4929.4 1902.37
  4953.4 1901.34  4968.4 1901.03  4969.4 1900.53  5011.4 1901.03  5013.6 1904.42
    5023 1905.05  5029.5 1908.73  5035.2 1910.26  5125.9 1914.47  5153.3 1920.83
  5170.9 1922.82  5241.8 1928.41  5308.8 1935.61  5393.8 1939.51  5403.1 1939.65
#Mann= 7 ,-1 , 0
  4596.9     .07       0  4798.4      .1       0  4953.4     .07       0
  4968.4     .05       0  5011.4     .07       0  5170.9    .035       0
  5393.8     .07       0
Bank Sta=4968.4,5011.4
XS Rating Curve= 0 ,0
Exp/Cntr=0.3,0.1

Type RM Length L Ch R = 1 ,15495   ,562,562,562
BEGIN DESCRIPTION:
Bear Creek 2 27.0
END DESCRIPTION:
XS GIS Cut Line= 3
        1829275.       13940225.        1828925.       13940025.
      1828175.53      13940031.2
#Sta/Elev= 30
  4601.5 1998.45  4733.2 1995.68  4770.7 1991.37  4813.9 1989.49  4844.1 1984.73
    4857 1980.33  4866.4 1966.47  4872.9 1952.35  4894.5 1938.92    4901 1926.54
  4910.3 1912.03  4916.1 1906.96    4924 1904.83  4959.3 1902.95  4960.1 1901.51
  4961.1 1901.01  5003.1 1901.51  5004.6 1907.39  5014.6 1910.57  5034.6 1914.23
  5047.6    1914  5074.6 1918.32  5146.3 1921.55  5212.7 1929.11  5274.6 1934.14
    5441 1936.87  5526.5 1939.79  5544.6 1942.19  5654.6 1947.62  5754.1  1957.6
#Mann= 9 ,-1 , 0
  4601.5     .07       0  4844.1      .1       0  4960.1     .05       0
  5003.1      .1       0  5047.6     .07       0  5146.3    .035       0
  5212.7     .07       0    5441    .035       0  5526.5     .07       0
Bank Sta=4960.1,5003.1
XS Rating Curve= 0 ,0
Exp/Cntr=0.3,0.1

Type RM Length L Ch R = 1 ,14933   ,548,548,548
BEGIN DESCRIPTION:
Bear Creek 2 26.0
END DESCRIPTION:
XS GIS Cut Line= 3
      1829425.01       13939475.        1829025.       13939525.
      1828118.11     13939757.32
#Sta/Elev= 30
  4601.4 2005.94  4664.8 1999.45  4699.7 1996.29  4886.1 1978.13  4893.7 1974.21
  4903.7 1934.57  4913.8 1913.42  4923.9 1910.13  4933.3 1908.55  4961.7 1902.72
  4962.8 1898.78  4963.8 1898.28  5005.9 1898.78  5007.1 1903.88  5027.5 1906.62
  5035.5 1909.56  5045.8 1912.05  5097.4 1917.89  5136.4 1919.39  5241.9 1923.06
  5283.2 1926.96  5341.7 1930.54  5438.1 1931.39  5593.5 1936.44  5644.5 1940.22
  5710.7 1942.63  5751.5 1946.96  5758.1 1948.61  5768.4 1949.72  5940.7  1959.2
#Mann= 8 ,-1 , 0
  4601.4      .1       0  4664.8     .07       0  4699.7      .1       0
  4933.3     .07       0  4962.8     .05       0  5005.9     .07       0
  5136.4    .035       0  5341.7     .07       0
Bank Sta=4962.8,5005.9
XS Rating Curve= 0 ,0
Exp/Cntr=0.3,0.1

Type RM Length L Ch R = 1 ,14385   ,564,564,564
BEGIN DESCRIPTION:
Bear Creek 2 25.0
END DESCRIPTION:
XS GIS Cut Line= 3
      1829275.04     13939125.01        1828875.       13939025.
      1828075.01       13939075.
#Sta/Elev= 30
  4587.7 1984.09  4739.6 1973.63  4835.1 1968.48  4845.4 1964.92  4853.2 1960.36
  4858.3 1961.01    4866  1955.7  4876.4 1937.61  4886.7 1914.89  4894.4 1909.81
  4899.5 1911.52  4917.6 1904.12  4935.6 1901.03  4940.8  1901.9  4958.8 1898.83
  4960.4 1896.83  4961.4 1896.33  5003.6 1896.83  5010.1 1900.55  5060.2 1908.02
  5077.7 1912.92  5237.7 1917.99  5260.6 1920.96  5380.8 1925.64  5551.1 1936.52
  5601.2 1942.92  5621.3 1947.71    5724 1960.74  5771.6 1969.75  5801.6 1972.53
#Mann= 5 ,-1 , 0
  4587.7     .07       0  4739.6      .1       0  4960.4     .05       0
  5003.6      .1       0  5237.7     .07       0
Bank Sta=4960.4,5003.6
XS Rating Curve= 0 ,0
Exp/Cntr=0.3,0.1

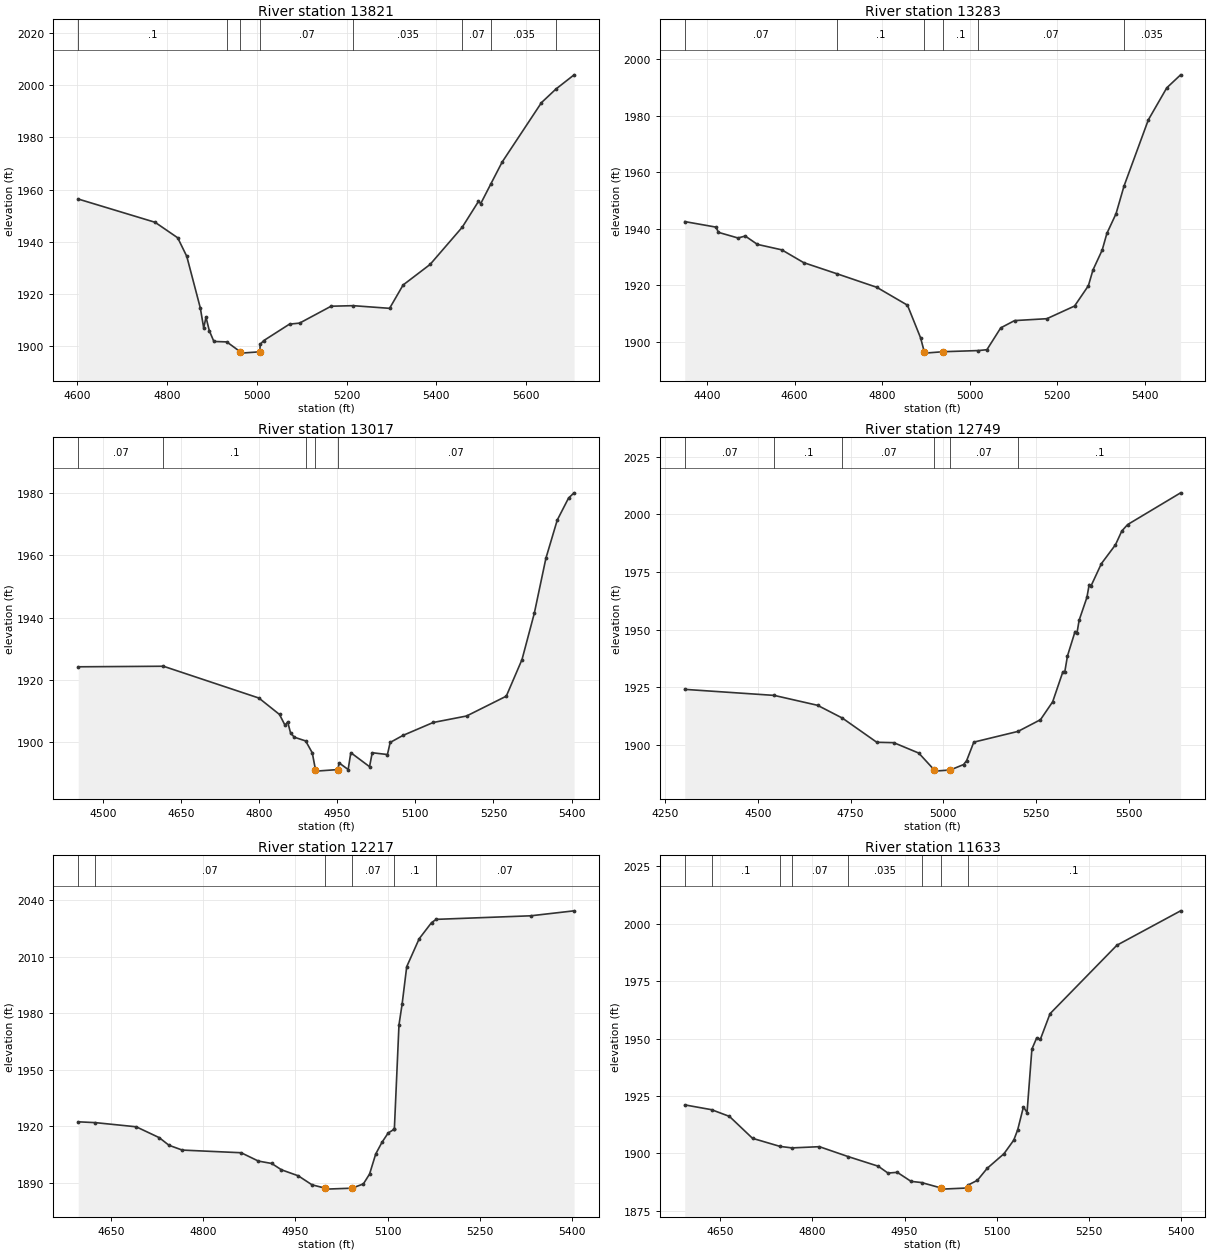
Type RM Length L Ch R = 1 ,13821   ,538,538,538
BEGIN DESCRIPTION:
Bear Creek 2 24.0
END DESCRIPTION:
XS GIS Cut Line= 3
      1828974.99       13938625.        1828575.       13938575.
      1827874.99       13938525.
#Sta/Elev= 30
    4602 1956.38  4773.3 1947.47  4823.7 1941.53  4843.9 1934.42  4874.1 1914.63
  4881.6 1906.99  4886.7  1911.1  4894.2 1905.89  4904.3 1901.82    4933 1901.65
  4963.3 1897.85  4964.3 1897.35  5006.5 1897.85  5007.6 1900.73  5015.1 1902.12
  5072.8 1908.46  5095.3 1908.85  5165.5 1915.32  5214.6 1915.53  5295.8 1914.51
  5325.9 1923.45  5386.1 1931.33  5457.6 1945.57  5493.8 1955.45  5498.9 1954.64
  5521.5  1962.2  5546.5 1970.52  5634.2 1993.31  5666.6 1998.54  5706.9 2003.96
#Mann= 8 ,-1 , 0
    4602      .1       0    4933     .07       0  4963.3     .05       0
  5006.5     .07       0  5214.6    .035       0  5457.6     .07       0
  5521.5    .035       0  5666.6     .07       0
Bank Sta=4963.3,5006.5
XS Rating Curve= 0 ,0
Exp/Cntr=0.3,0.1

Type RM Length L Ch R = 1 ,13283   ,266,266,266
BEGIN DESCRIPTION:
Bear Creek 2 23.0
END DESCRIPTION:
XS GIS Cut Line= 4
      1828943.16     13938292.57       1828605.9     13938121.75
        1828325.       13938125.      1827875.02     13938274.99
#Sta/Elev= 30
  4348.8 1942.55  4420.2 1940.59  4425.8 1938.74  4470.4 1936.75  4487.1 1937.43
  4514.9 1934.48  4570.6 1932.55  4620.7 1928.02  4697.4 1924.05  4787.8 1919.29
  4857.8 1912.97  4887.8 1901.42  4896.2 1896.51  4897.2 1896.01  4939.4 1896.51
    5020 1896.92  5039.4 1897.22    5071 1904.95  5102.6 1907.52  5176.4 1908.19
  5239.7 1912.67  5271.3 1919.85  5281.8 1925.44  5302.9 1932.49  5313.5 1938.34
  5334.5 1945.34  5352.7  1955.1  5408.3 1978.54  5450.5 1989.88  5482.1 1994.47
#Mann= 6 ,-1 , 0
  4348.8     .07       0  4697.4      .1       0  4896.2     .05       0
  4939.4      .1       0    5020     .07       0  5352.7    .035       0
Bank Sta=4896.2,4939.4
XS Rating Curve= 0 ,0
Exp/Cntr=0.3,0.1

Type RM Length L Ch R = 1 ,13017   ,268,268,268
BEGIN DESCRIPTION:
Bear Creek 2 22.1
END DESCRIPTION:
XS GIS Cut Line= 4
       1828747.2     13938040.21      1828356.56      13937894.8
      1828179.69     13937939.29      1827855.27     13938078.17
#Sta/Elev= 30
  4452.8 1924.11  4616.4 1924.29  4799.7 1914.04  4839.3 1908.74  4849.7 1905.32
    4855 1906.31  4860.6 1902.75  4867.8 1901.41  4889.5 1900.21  4902.2 1896.38
  4908.3 1890.98  4909.3 1890.48  4951.5 1890.98  4953.7 1893.13  4971.1    1891
  4976.2 1896.43  5012.2 1891.91  5017.3 1896.41  5046.5 1895.83  5051.8 1899.73
  5076.3 1901.99  5134.4 1906.16  5198.5 1908.25  5274.7 1914.64  5304.9 1926.45
  5328.5 1941.36  5350.8 1959.11  5372.6 1971.42  5394.3 1978.52  5404.9 1980.19
#Mann= 5 ,-1 , 0
  4452.8     .07       0  4616.4      .1       0  4889.5     .07       0
  4908.3     .05       0  4951.5     .07       0
Bank Sta=4908.3,4951.5
XS Rating Curve= 0 ,0
Exp/Cntr=0.3,0.1

Type RM Length L Ch R = 1 ,12749   ,532,532,532
BEGIN DESCRIPTION:
Bear Creek 2 22.0
END DESCRIPTION:
XS GIS Cut Line= 3
      1828806.05     13937971.04        1828175.       13937675.
      1827563.38     13937488.35
#Sta/Elev= 30
  4302.8 1924.09  4543.9 1921.47  4660.7 1917.18  4727.8 1911.62  4820.4 1901.15
  4866.1 1900.98  4933.6 1896.46  4975.4 1889.14  4976.4 1888.64  5018.7 1889.14
  5054.3 1891.49  5062.6  1893.2  5081.9 1901.21  5201.2 1905.87  5261.6 1910.94
  5294.4 1918.69    5322 1931.73  5327.2 1931.78  5334.4 1938.62  5354.8 1949.16
  5360.1 1948.65  5365.8 1954.07  5386.7 1963.93  5392.9 1969.54  5398.1 1969.02
  5425.7 1978.58  5463.7 1986.76  5480.8 1992.75  5496.5 1995.53  5639.3 2009.29
#Mann= 6 ,-1 , 0
  4302.8     .07       0  4543.9      .1       0  4727.8     .07       0
  4975.4     .05       0  5018.7     .07       0  5201.2      .1       0
Bank Sta=4975.4,5018.7
XS Rating Curve= 0 ,0
Exp/Cntr=0.3,0.1

Type RM Length L Ch R = 1 ,12217   ,584,584,584
BEGIN DESCRIPTION:
Bear Creek 2 21.0
END DESCRIPTION:
XS GIS Cut Line= 3
        1828725.       13937775.        1828525.       13937425.
        1828475.     13937025.03
#Sta/Elev= 30
  4596.9 1922.44  4624.8    1922  4691.2 1919.79  4728.6 1914.03  4744.5 1909.97
  4766.1 1907.42  4861.8 1906.01  4889.9 1901.57  4911.5 1900.31  4927.3 1896.95
  4954.7 1893.75    4977 1888.97  4998.5 1887.18  4999.5 1886.68  5041.9 1887.18
  5060.5 1889.44  5070.6  1894.7  5080.6 1905.36  5090.7 1911.52  5100.8 1916.49
  5110.7 1918.51  5110.9 1918.55  5118.4 1973.92  5123.5 1984.95    5131 2004.85
  5151.2 2019.66  5171.3 2028.23  5178.9 2029.98  5332.6 2031.87  5403.1 2034.51
#Mann= 6 ,-1 , 0
  4596.9      .1       0  4624.8     .07       0  4998.5     .05       0
  5041.9     .07       0  5110.7      .1       0  5178.9     .07       0
Bank Sta=4998.5,5041.9
XS Rating Curve= 0 ,0
Exp/Cntr=0.3,0.1

Type RM Length L Ch R = 1 ,11633   ,559,559,559
BEGIN DESCRIPTION:
Bear Creek 2 20.0
END DESCRIPTION:
XS GIS Cut Line= 3
      1828874.99     13937775.02        1829075.       13937425.
      1829274.98     13937075.04
#Sta/Elev= 30
  4592.7 1921.15  4636.4 1919.05  4665.4 1916.13  4702.9  1906.6  4747.6 1903.08
    4767 1902.43  4811.6 1902.96  4858.8 1898.61  4907.3 1894.46  4923.1 1891.48
  4938.2  1891.8  4960.6 1887.87  4977.7 1887.35  5009.4 1884.99  5010.4 1884.49
  5052.8 1884.99  5053.4 1886.26  5068.5 1888.33  5084.4 1893.54  5111.7 1899.89
  5127.6  1905.8    5134 1910.29  5143.4 1920.32  5149.2 1917.77  5157.1 1945.42
    5165 1950.35  5170.8 1949.63  5186.6 1960.83  5295.3 1990.62  5398.9 2005.59
#Mann= 8 ,-1 , 0
  4592.7     .07       0  4636.4      .1       0  4747.6    .035       0
    4767     .07       0  4858.8    .035       0  4977.7      .1       0
  5009.4     .05       0  5052.8      .1       0
Bank Sta=5009.4,5052.8
XS Rating Curve= 0 ,0
Exp/Cntr=0.3,0.1

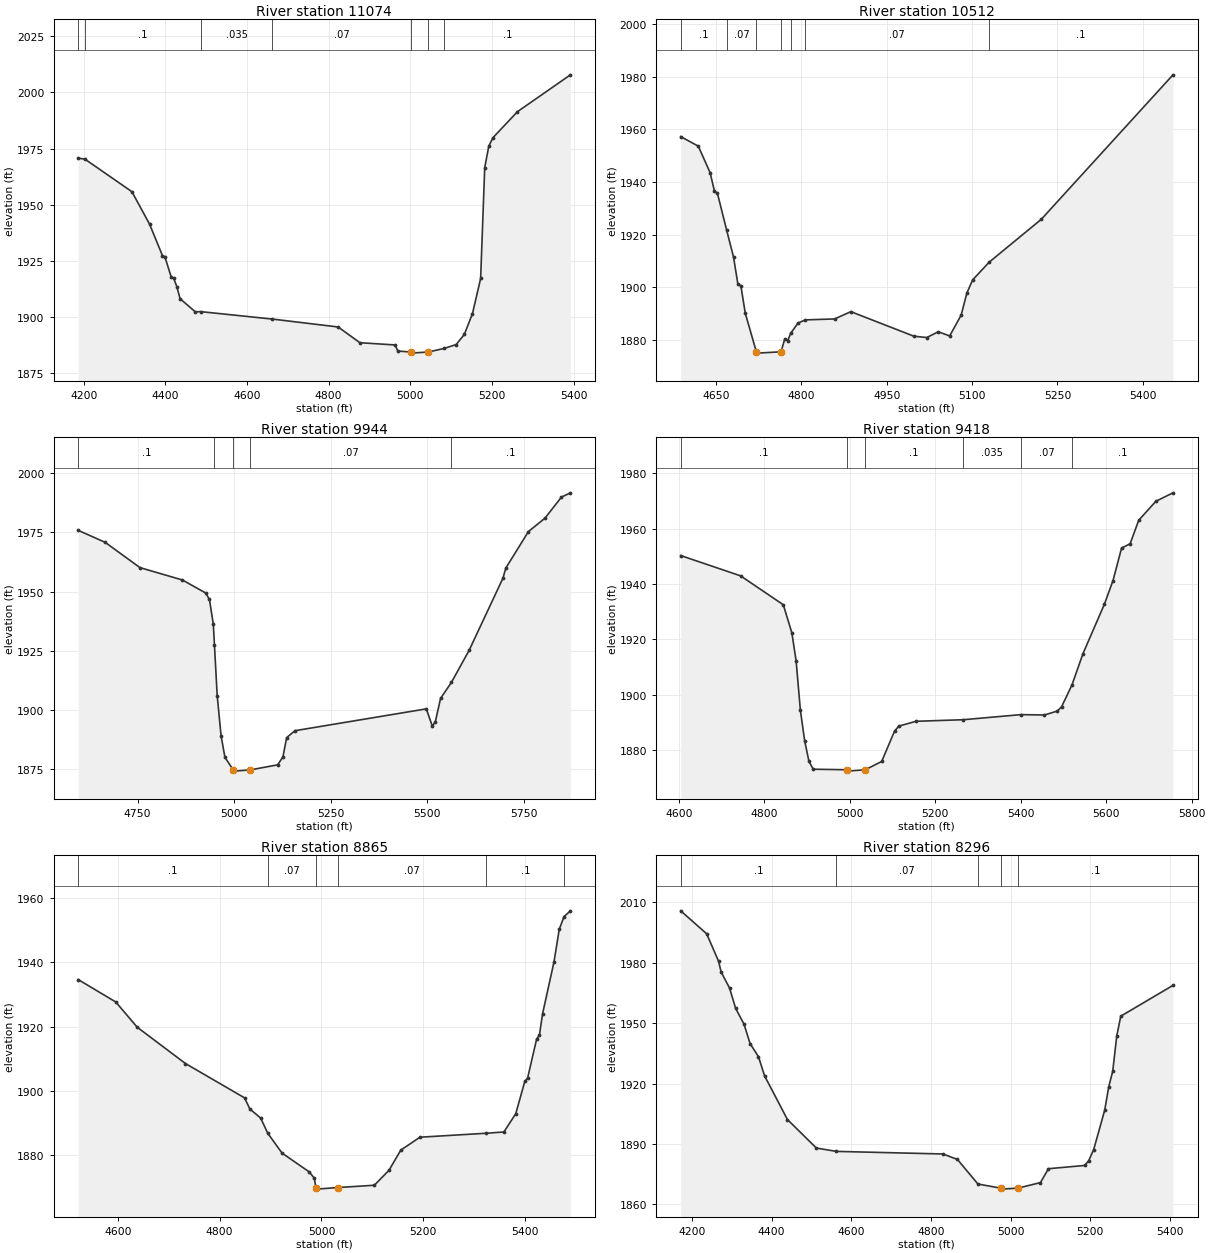
Type RM Length L Ch R = 1 ,11074   ,562,562,562
BEGIN DESCRIPTION:
Bear Creek 2 19.0
END DESCRIPTION:
XS GIS Cut Line= 3
      1829975.01     13938325.01        1829575.       13937625.
        1829575.     13937225.04
#Sta/Elev= 30
  4186.2 1970.73  4202.7 1970.31  4317.9  1955.8  4361.1 1941.35  4392.8 1927.32
  4398.6 1926.84  4414.4 1917.69  4420.2 1917.24  4428.1 1913.45    4436  1908.1
  4473.4 1902.25  4486.3 1902.36  4662.2 1899.04  4823.3 1895.52  4876.5 1888.51
  4962.9 1887.51  4969.4  1884.8  5000.7 1884.37  5001.7 1883.87  5044.1 1884.37
  5083.4 1885.98  5112.4  1887.7  5132.4 1892.18  5152.4 1901.48  5172.4 1917.12
  5182.4 1966.52  5192.4 1976.08  5202.4 1979.82  5262.4 1991.41  5392.4 2007.86
#Mann= 7 ,-1 , 0
  4186.2     .07       0  4202.7      .1       0  4486.3    .035       0
  4662.2     .07       0  5000.7     .05       0  5044.1     .07       0
  5083.4      .1       0
Bank Sta=5000.7,5044.1
XS Rating Curve= 0 ,0
Exp/Cntr=0.3,0.1

Type RM Length L Ch R = 1 ,10512   ,568,568,568
BEGIN DESCRIPTION:
Bear Creek 2 18.0
END DESCRIPTION:
XS GIS Cut Line= 3
      1830175.01     13938125.03        1830075.       13937725.
        1830025.     13937275.01
#Sta/Elev= 30
    4588 1957.26  4618.9 1953.64  4639.6 1943.61  4647.3 1936.57  4652.4 1935.86
  4668.7 1921.77  4680.8 1911.57  4688.5 1901.24  4693.7 1900.67  4701.4 1890.29
  4720.9 1875.57  4721.9 1875.07  4764.3 1875.57    4771 1880.55  4776.1 1879.79
  4781.2 1882.55  4794.2  1886.5  4807.1 1887.69  4858.6 1888.05    4887 1890.81
  4997.8 1881.49  5020.5 1880.99  5040.6 1883.17  5060.7 1881.61  5080.8 1889.47
  5090.9 1897.88    5101 1902.85  5130.1  1909.6  5221.7 1925.87  5453.1 1980.71
#Mann= 7 ,-1 , 0
    4588      .1       0  4668.7     .07       0  4720.9     .05       0
  4764.3     .07       0  4781.2    .035       0  4807.1     .07       0
  5130.1      .1       0
Bank Sta=4720.9,4764.3
XS Rating Curve= 0 ,0
Exp/Cntr=0.3,0.1

Type RM Length L Ch R = 1 ,9944    ,526,526,526
BEGIN DESCRIPTION:
Bear Creek 2 17.0
END DESCRIPTION:
XS GIS Cut Line= 3
        1830575.       13938325.        1830575.       13937925.
      1830125.02     13937175.04
#Sta/Elev= 30
  4596.2 1975.87  4666.2  1970.8  4756.2 1960.13  4866.2 1954.91  4926.2 1949.44
  4936.2  1946.7  4946.2 1936.17  4949.1 1927.46  4956.2 1906.13  4966.2 1889.24
  4976.2 1880.08  4997.8 1874.74  4998.8 1874.24  5041.3 1874.74  5112.8  1876.9
  5126.4 1880.24  5136.1 1888.38  5157.5  1891.3  5497.7 1900.52  5513.2 1893.24
    5521 1895.06  5534.6 1904.96  5562.6 1911.67  5608.4 1925.19  5695.9 1955.61
  5703.7 1959.99    5762 1975.34  5804.8 1980.99  5847.5 1989.88  5870.8  1991.7
#Mann= 5 ,-1 , 0
  4596.2      .1       0  4949.1     .07       0  4997.8     .05       0
  5041.3     .07       0  5562.6      .1       0
Bank Sta=4997.8,5041.3
XS Rating Curve= 0 ,0
Exp/Cntr=0.3,0.1

Type RM Length L Ch R = 1 ,9418    ,553,553,553
BEGIN DESCRIPTION:
Bear Creek 2 16.0
END DESCRIPTION:
XS GIS Cut Line= 3
        1830975.     13938025.02        1830975.       13937625.
        1830925.     13936874.98
#Sta/Elev= 30
  4604.6 1950.27  4744.6 1942.93  4844.6 1932.48  4864.6 1922.35  4874.6  1912.2
  4884.6 1894.32  4894.6 1883.27  4904.6 1875.88  4914.6    1873  4992.9 1872.81
  4993.9 1872.31  5036.4 1872.81  5074.8  1875.8  5104.8 1886.76  5114.9 1888.58
  5154.9 1890.33  5265.5  1890.9  5400.7 1892.74  5455.6 1892.61  5485.7 1894.03
  5495.7 1895.58  5519.8 1903.41  5545.8 1914.83  5595.9 1932.69    5616 1941.23
    5636 1952.95  5656.1 1954.55  5676.1 1963.02  5716.2 1969.89  5756.3 1972.95
#Mann= 6 ,-1 , 0
  4604.6      .1       0  4992.9     .05       0  5036.4      .1       0
  5265.5    .035       0  5400.7     .07       0  5519.8      .1       0
Bank Sta=4992.9,5036.4
XS Rating Curve= 0 ,0
Exp/Cntr=0.3,0.1

Type RM Length L Ch R = 1 ,8865    ,569,569,569
BEGIN DESCRIPTION:
Bear Creek 2 15.0
END DESCRIPTION:
XS GIS Cut Line= 3
        1831275.     13937874.99        1831425.       13937425.
      1831224.99     13936974.98
#Sta/Elev= 30
  4522.1 1934.66  4595.9 1927.67    4638  1919.8  4732.9 1908.45  4848.9 1897.75
  4859.4 1894.26  4880.5 1891.45  4894.5 1886.69  4922.6 1880.51  4975.3 1874.71
  4985.9 1872.72    4989 1869.77    4990 1869.27  5032.5 1869.77  5103.8 1870.48
  5132.5 1875.14  5155.8 1881.45  5193.4 1885.47    5324 1886.71  5358.2  1887.1
  5381.5 1892.79  5399.3 1902.88  5404.7 1903.84  5422.5 1916.07    5428  1917.3
  5434.2 1923.99  5456.7 1940.21    5467 1950.36  5476.4 1954.31  5488.9  1956.1
#Mann= 6 ,-1 , 0
  4522.1      .1       0  4894.5     .07       0    4989     .05       0
  5032.5     .07       0    5324      .1       0  5476.4     .07       0
Bank Sta=4989,5032.5
XS Rating Curve= 0 ,0
Exp/Cntr=0.3,0.1

Type RM Length L Ch R = 1 ,8296    ,506,506,506
BEGIN DESCRIPTION:
Bear Creek 2 14.0
END DESCRIPTION:
XS GIS Cut Line= 3
      1832325.02     13937825.03        1831875.       13937125.
        1831825.     13936725.01
#Sta/Elev= 30
  4172.1 2005.84  4237.2 1994.44  4267.2 1980.76  4273.5 1975.44  4294.6 1967.51
  4309.8 1957.48    4331 1949.49  4346.2 1939.89  4367.3 1933.34  4382.5 1923.88
  4439.9 1902.15  4512.6 1887.97  4562.7 1886.32  4830.3 1885.03  4866.6  1882.3
  4917.9 1870.11  4974.7 1868.07  4975.7 1867.57  5018.8 1868.07  5074.8 1870.82
    5095 1877.72  5185.7 1879.33  5195.8 1881.66  5208.4 1887.21  5236.1 1906.81
  5246.2 1918.43  5256.2 1926.15  5266.3 1943.63  5276.4  1953.5  5407.4  1968.8
#Mann= 5 ,-1 , 0
  4172.1      .1       0  4562.7     .07       0  4917.9      .1       0
  4974.7     .05       0  5018.8      .1       0
Bank Sta=4974.7,5018.8
XS Rating Curve= 0 ,0
Exp/Cntr=0.3,0.1

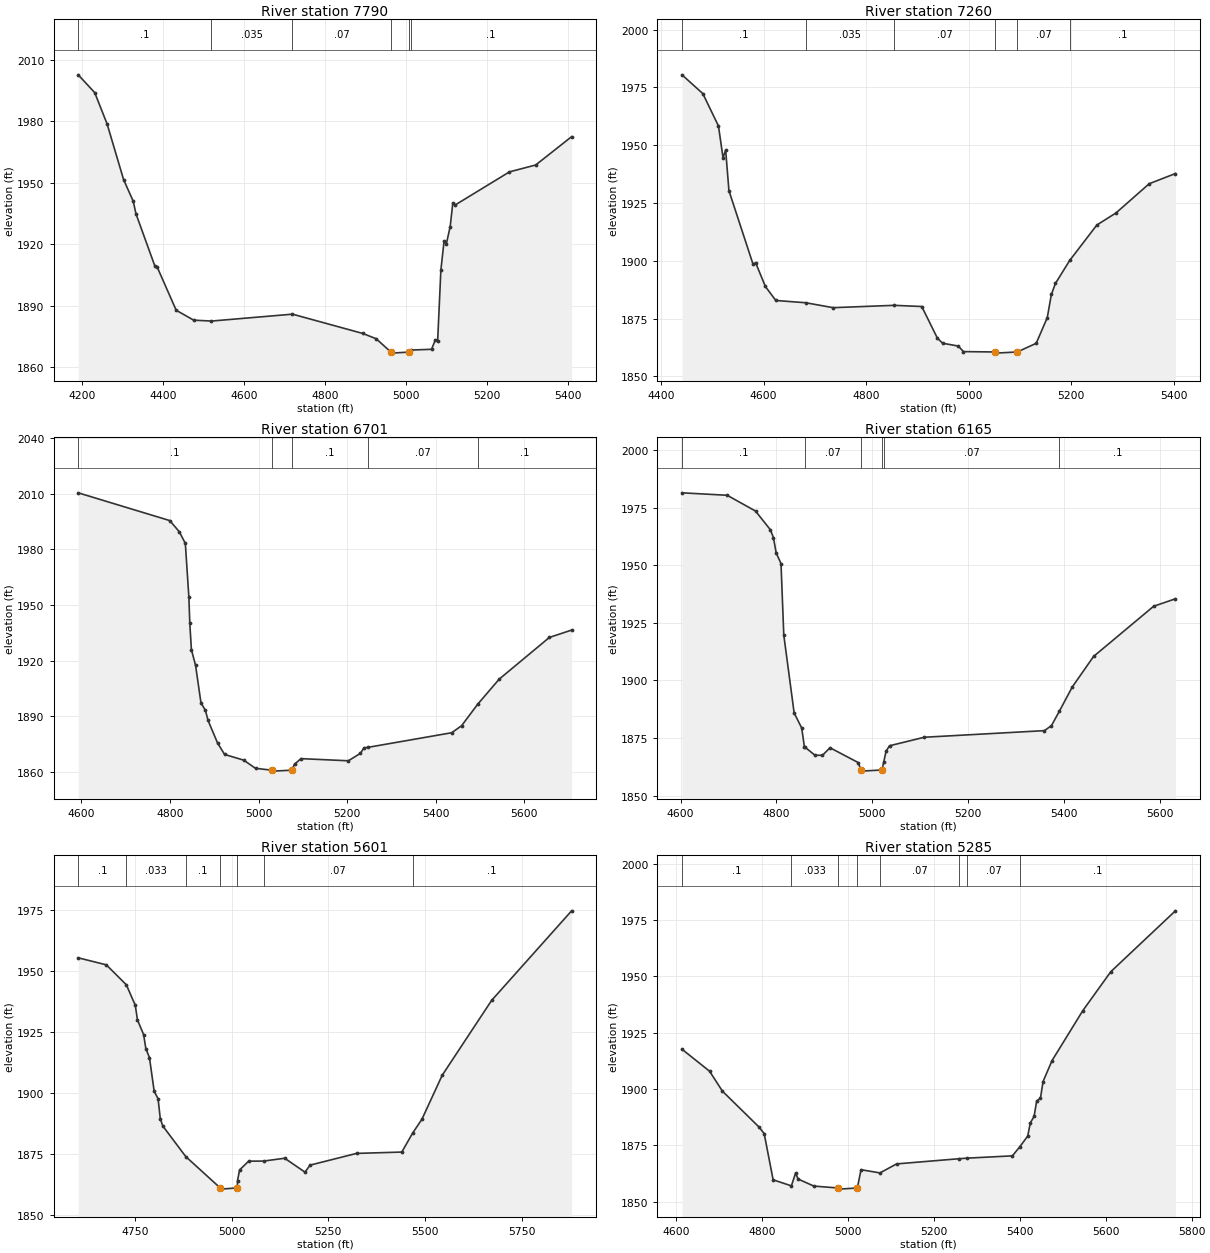
Type RM Length L Ch R = 1 ,7790    ,530,530,530
BEGIN DESCRIPTION:
Bear Creek 2 13.0
END DESCRIPTION:
XS GIS Cut Line= 3
      1832425.01     13937775.03        1832275.       13936975.
      1832074.99     13936624.99
#Sta/Elev= 30
  4191.1 2002.59  4231.8 1993.91  4262.4 1978.61  4303.1 1951.42  4326.8 1940.94
  4333.6 1934.76  4380.2 1909.29  4385.3 1909.06  4432.8 1887.71    4476 1882.87
  4519.7 1882.44  4719.7  1885.8  4893.2 1876.38  4926.2 1873.79  4962.6 1867.29
  4963.6 1866.79  5006.8 1867.29  5011.2 1868.29  5062.7 1868.66    5072 1873.19
  5077.8  1872.9  5085.7 1907.31  5093.6 1921.49  5099.4 1920.27  5108.7 1928.55
  5115.2 1940.18    5121 1939.08  5254.9 1955.24  5319.6 1958.59  5408.2 1972.41
#Mann= 6 ,-1 , 0
  4191.1      .1       0  4519.7    .035       0  4719.7     .07       0
  4962.6     .05       0  5006.8     .07       0  5011.2      .1       0
Bank Sta=4962.6,5006.8
XS Rating Curve= 0 ,0
Exp/Cntr=0.3,0.1

Type RM Length L Ch R = 1 ,7260    ,559,559,559
BEGIN DESCRIPTION:
Bear Creek 2 12.0
END DESCRIPTION:
XS GIS Cut Line= 3
        1832625.     13937674.98        1832725.       13937125.
        1832525.     13936775.01
#Sta/Elev= 30
    4441 1980.43  4481.6 1972.31  4512.1 1958.31    4521 1944.55  4526.1 1947.89
  4532.5 1930.33  4579.5 1898.52  4584.5 1899.18  4603.6 1888.88  4623.9 1882.83
  4682.3 1881.85  4735.7 1879.72  4854.4 1880.73  4908.5 1880.22    4939 1866.53
  4949.2 1864.34  4979.7 1863.12  4989.8 1860.72  5050.6 1860.56  5051.6 1860.06
  5094.8 1860.56  5131.7 1864.31  5153.3 1875.44  5161.2 1885.43  5169.2 1890.22
    5197 1900.15  5249.8 1915.45  5287.2 1920.68    5352 1933.33  5403.1 1937.73
#Mann= 6 ,-1 , 0
    4441      .1       0  4682.3    .035       0  4854.4     .07       0
  5050.6     .05       0  5094.8     .07       0    5197      .1       0
Bank Sta=5050.6,5094.8
XS Rating Curve= 0 ,0
Exp/Cntr=0.3,0.1

Type RM Length L Ch R = 1 ,6701    ,536,536,536
BEGIN DESCRIPTION:
Bear Creek 2 11.0
END DESCRIPTION:
XS GIS Cut Line= 3
      1833424.99     13937474.98        1833225.       13937125.
      1832775.02     13936575.02
#Sta/Elev= 30
  4592.9 2010.47  4799.5  1995.5  4821.1 1989.47  4834.7 1983.19  4842.7 1954.15
  4844.8    1940  4848.4 1925.84  4857.8 1917.37    4870 1897.14  4880.1 1893.05
  4885.9 1887.69  4907.5 1875.46  4923.3 1869.31  4966.5 1866.23  4993.1 1861.82
  5030.6 1860.81  5031.6 1860.31  5074.8 1860.81  5081.4 1864.09  5095.8 1867.05
  5202.7 1865.89    5230 1869.93  5237.9 1872.86  5247.9 1873.18    5436 1881.03
  5458.3 1884.82  5494.5 1896.37    5543 1909.91  5656.4 1932.44  5706.6 1936.42
#Mann= 5 ,-1 , 0
  4592.9      .1       0  5030.6     .05       0  5074.8      .1       0
  5247.9     .07       0  5494.5      .1       0
Bank Sta=5030.6,5074.8
XS Rating Curve= 0 ,0
Exp/Cntr=0.3,0.1

Type RM Length L Ch R = 1 ,6165    ,564,564,564
BEGIN DESCRIPTION:
Bear Creek 2 10.0
END DESCRIPTION:
XS GIS Cut Line= 3
      1833675.01     13937025.02        1833475.       13936675.
      1832925.03     13936375.02
#Sta/Elev= 30
  4602.9 1981.42  4697.2 1980.36  4756.3 1973.51  4787.2 1965.41  4793.7 1962.02
  4799.4 1955.33  4809.5 1950.72  4815.3 1919.64  4836.9 1885.87  4852.7 1879.31
  4858.5 1870.87  4860.2 1870.89  4880.1 1867.54  4895.9 1867.43  4911.7 1870.76
  4970.8 1864.29    4976  1861.1    4977  1860.6  5020.2  1861.1  5023.8 1864.52
  5028.8 1869.27  5035.9 1871.61  5108.6 1875.31  5359.2 1878.18  5373.9 1880.36
  5390.4 1886.64  5417.5  1897.2  5461.7 1910.38    5587 1932.16  5632.5 1935.42
#Mann= 6 ,-1 , 0
  4602.9      .1       0  4860.2     .07       0    4976     .05       0
  5020.2     .07       0  5023.8     .07       0  5390.4      .1       0
Bank Sta=4976,5020.2
XS Rating Curve= 0 ,0
Exp/Cntr=0.3,0.1

Type RM Length L Ch R = 1 ,5601    ,316,316,316
BEGIN DESCRIPTION:
Bear Creek 2 9.0
END DESCRIPTION:
XS GIS Cut Line= 3
        1833875.     13936524.99        1833675.       13936175.
      1833325.01     13935375.01
#Sta/Elev= 30
  4602.9 1955.45  4675.6 1952.57  4727.4  1944.4  4750.5 1936.03  4756.2 1929.98
  4772.1    1924  4777.8  1918.3  4787.2 1914.56  4799.4  1900.8  4809.5 1897.73
  4815.2 1889.55  4821.7 1886.57  4881.2 1874.02  4970.2 1861.21  4971.2 1860.71
  5014.5 1861.21    5015  1864.2  5020.4 1868.58  5043.8 1872.16  5082.4  1872.2
    5137 1873.36  5189.6 1867.66  5202.5 1870.53  5322.9 1875.34  5439.9 1875.89
  5467.9 1883.64  5492.1 1889.36  5544.4 1907.33  5672.2 1937.99  5879.2 1974.69
#Mann= 7 ,-1 , 0
  4602.9      .1       0  4727.4    .033       0  4881.2      .1       0
  4970.2     .05       0  5014.5      .1       0  5082.4     .07       0
  5467.9      .1       0
Bank Sta=4970.2,5014.5
XS Rating Curve= 0 ,0
Exp/Cntr=0.3,0.1

Type RM Length L Ch R = 1 ,5285    ,249,249,249
BEGIN DESCRIPTION:
Bear Creek 2 8.1
END DESCRIPTION:
XS GIS Cut Line= 5
      1833984.51     13936218.92      1833996.66     13936040.06
      1833968.88     13936001.86      1833734.51     13935856.03
      1833361.86     13935329.13
#Sta/Elev= 30
  4614.3 1917.61  4678.4 1907.88  4708.4 1899.01  4793.6 1883.08  4805.5 1880.18
  4826.3  1859.7  4868.8 1857.01  4878.5 1862.66  4884.4 1860.04    4921 1856.91
  4977.9 1856.06  4978.9 1855.56  5022.2 1856.06  5030.8 1864.18  5074.8 1862.75
  5113.6 1866.75  5259.7 1869.06  5277.1  1869.3  5382.9 1870.32  5400.4 1874.39
  5418.6 1879.11  5424.7 1884.96  5433.4 1887.81  5439.5 1894.68  5448.2 1895.82
  5454.3  1903.3  5475.2 1912.59  5546.8 1934.75  5611.9 1952.02  5762.2 1979.02
#Mann= 8 ,-1 , 0
  4614.3      .1       0  4868.8    .033       0  4977.9     .05       0
  5022.2     .07       0  5074.8     .07       0  5259.7    .035       0
  5277.1     .07       0  5400.4      .1       0
Bank Sta=4977.9,5022.2
XS Rating Curve= 0 ,0
Exp/Cntr=0.3,0.1