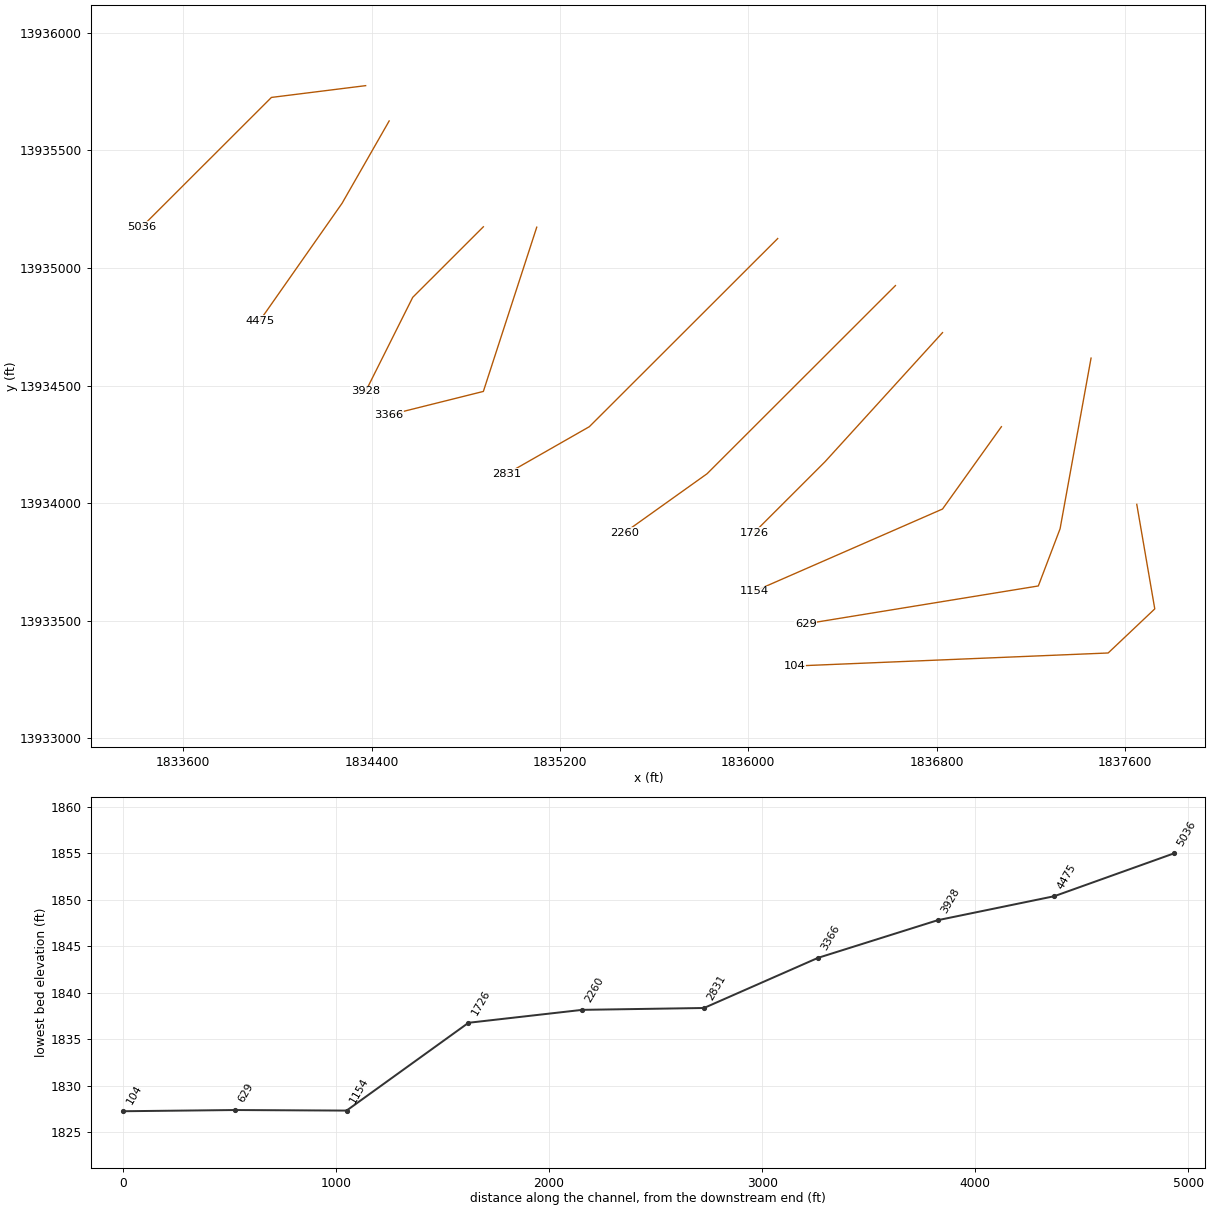
HEC-RAS study Bear Creek 2.prj: Bear Creek 2 Base Level Engineering

--- Bear Creek 2.g01 (geometry) --- (continued)

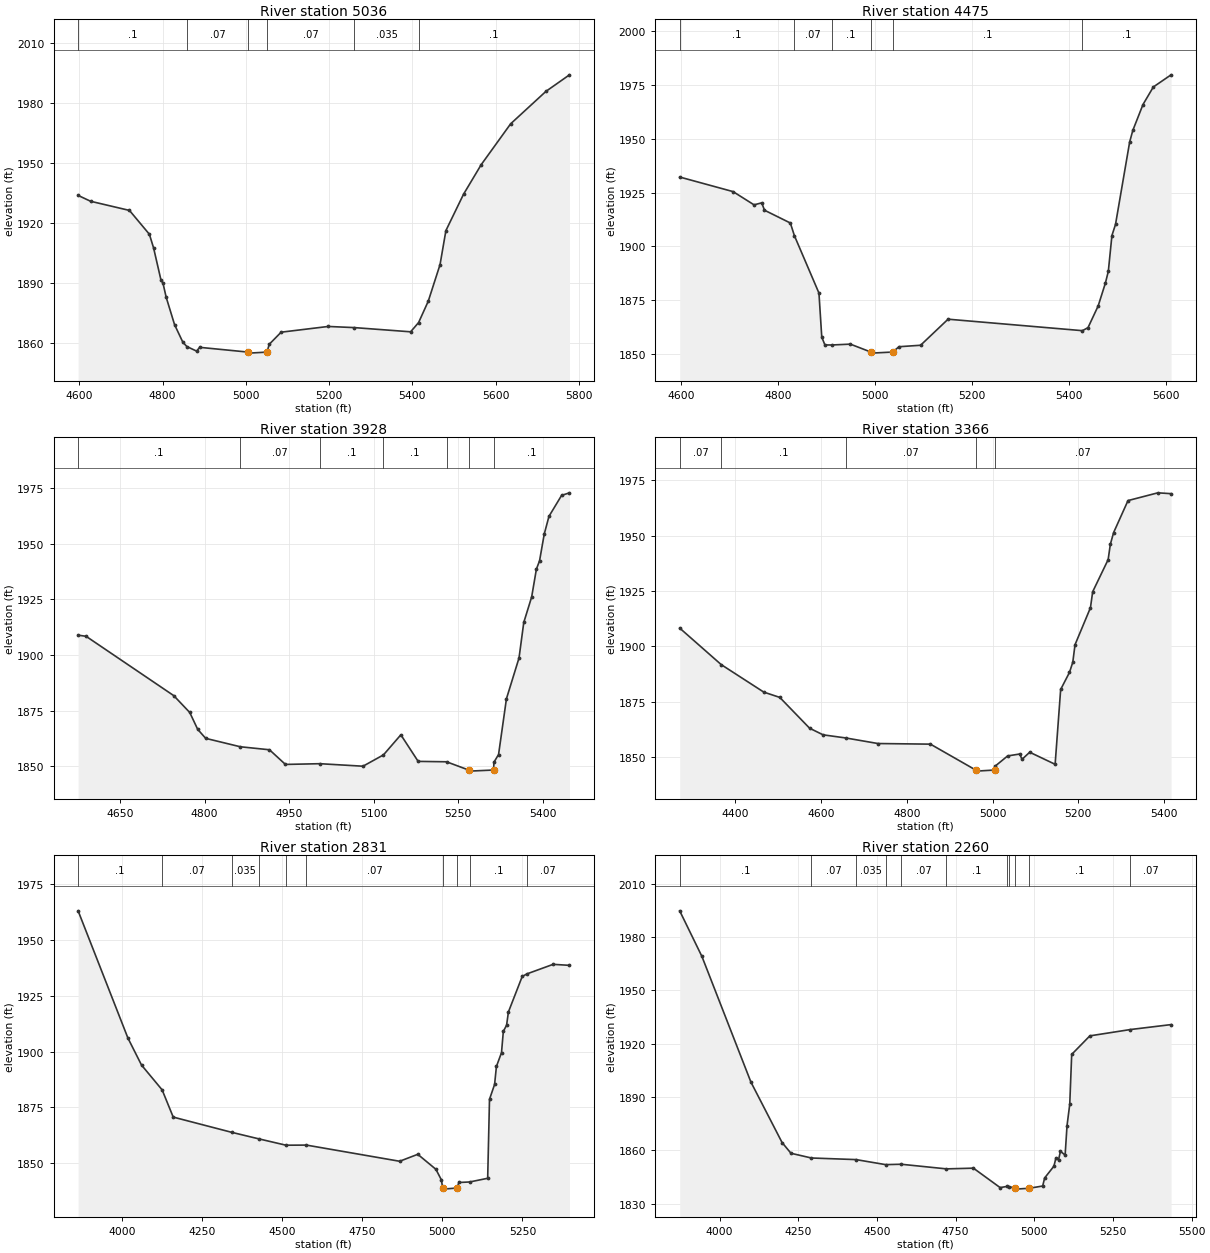
Type RM Length L Ch R = 1 ,5036    ,561,561,561
BEGIN DESCRIPTION:
Bear Creek 2 8.0
END DESCRIPTION:
XS GIS Cut Line= 3
      1834374.97       13935775.        1833975.       13935725.
        1833425.       13935175.
#Sta/Elev= 30
  4596.9 1933.74  4627.1  1930.8  4720.3 1926.24  4768.2 1914.33  4778.3 1907.49
  4795.9 1891.59  4800.9 1889.88  4808.5  1882.9  4828.7 1869.18  4848.8 1860.33
  4858.4 1858.24  4881.6 1855.97  4889.1 1857.85    5006 1855.46    5007 1854.96
  5050.5 1855.46  5056.5 1859.43  5084.8 1865.42    5198 1868.28  5260.6 1867.71
    5396 1865.61  5415.2 1870.24  5438.4 1880.91  5466.7 1899.18  5480.8 1916.18
  5523.2 1934.34  5565.7 1949.12  5636.4 1969.51  5721.2 1985.71  5777.8 1993.97
#Mann= 6 ,-1 , 0
  4596.9      .1       0  4858.4     .07       0    5006     .05       0
  5050.5     .07       0  5260.6    .035       0  5415.2      .1       0
Bank Sta=5006,5050.5
XS Rating Curve= 0 ,0
Exp/Cntr=0.3,0.1

Type RM Length L Ch R = 1 ,4475    ,547,547,547
BEGIN DESCRIPTION:
Bear Creek 2 7.0
END DESCRIPTION:
XS GIS Cut Line= 3
        1834475.       13935625.        1834275.       13935275.
      1833925.02     13934775.03
#Sta/Elev= 30
  4597.7 1932.24  4707.8 1925.46    4751 1919.31  4766.9 1920.23  4772.6 1916.81
  4825.9 1910.86  4834.3 1904.95  4884.9 1878.29  4890.7  1857.8  4897.2 1854.18
  4910.8 1854.14  4949.7 1854.54    4992 1850.86    4993 1850.36  5036.6 1850.86
  5050.1 1853.34  5094.5 1854.02  5151.2 1866.14  5428.2  1860.8  5439.8 1862.21
  5460.7 1872.28  5475.6 1882.89  5481.7 1888.41  5489.1 1905.03  5496.5  1910.2
  5525.7 1948.55  5532.2 1953.92  5553.2 1965.96  5574.5 1974.11  5611.1 1979.76
#Mann= 6 ,-1 , 0
  4597.7      .1       0  4834.3     .07       0  4910.8      .1       0
    4992     .05       0  5036.6      .1       0  5428.2      .1       0
Bank Sta=4992,5036.6
XS Rating Curve= 0 ,0
Exp/Cntr=0.3,0.1

Type RM Length L Ch R = 1 ,3928    ,562,562,562
BEGIN DESCRIPTION:
Bear Creek 2 6.0
END DESCRIPTION:
XS GIS Cut Line= 3
      1834874.99     13935174.99        1834575.       13934875.
      1834374.98     13934474.97
#Sta/Elev= 30
  4575.8 1908.89  4589.9 1908.39  4745.5  1881.7  4773.8 1874.14  4787.9 1866.56
  4802.1 1862.51  4863.5 1858.73  4915.2 1857.38  4943.5 1850.79  5004.6 1851.12
  5081.1 1849.99  5117.4 1855.09  5148.2  1864.1  5178.9 1852.16  5229.2 1851.98
  5268.4 1848.28  5269.4 1847.78    5313 1848.28  5313.1 1851.69  5321.5 1855.25
  5335.5 1880.34  5357.8 1898.65  5366.2  1914.6  5380.2 1926.07  5388.6 1938.57
  5394.2 1942.32  5402.5 1954.32  5410.9 1962.31  5433.3 1971.72  5447.3 1972.87
#Mann= 7 ,-1 , 0
  4575.8      .1       0  4863.5     .07       0  5004.6      .1       0
  5117.4      .1       0  5229.2      .1       0  5268.4     .05       0
    5313      .1       0
Bank Sta=5268.4,5313
XS Rating Curve= 0 ,0
Exp/Cntr=0.3,0.1

Type RM Length L Ch R = 1 ,3366    ,535,535,535
BEGIN DESCRIPTION:
Bear Creek 2 5.0
END DESCRIPTION:
XS GIS Cut Line= 3
      1835101.69     13935173.26        1834875.       13934475.
      1834475.04     13934375.01
#Sta/Elev= 30
  4270.2  1908.3  4367.1 1891.81  4466.4  1879.4  4503.7 1877.01  4573.3  1863.1
  4604.8 1860.11  4657.1 1858.72  4732.7 1856.19  4855.2 1855.91  4960.8 1844.23
  4961.8 1843.73  5005.4 1844.23  5006.9 1846.09  5035.3 1850.59  5063.6 1851.46
  5068.8 1849.05  5086.8 1852.26  5146.1 1846.81    5159 1880.59  5179.6 1888.31
  5187.3 1892.89  5192.5 1900.79  5228.5 1917.49  5233.7 1924.71  5269.8 1939.22
  5274.9 1946.12  5282.6 1951.44  5316.1 1965.86  5385.7 1969.36  5416.6 1968.98
#Mann= 5 ,-1 , 0
  4270.2     .07       0  4367.1      .1       0  4657.1     .07       0
  4960.8     .05       0  5005.4     .07       0
Bank Sta=4960.8,5005.4
XS Rating Curve= 0 ,0
Exp/Cntr=0.3,0.1

Type RM Length L Ch R = 1 ,2831    ,571,571,571
BEGIN DESCRIPTION:
Bear Creek 2 4.0
END DESCRIPTION:
XS GIS Cut Line= 3
      1836125.02     13935125.02        1835325.       13934325.
      1834975.01     13934125.01
#Sta/Elev= 30
  3862.6  1963.1  4018.2 1906.04  4060.6 1893.96    4125 1882.83  4159.6 1870.63
  4341.8 1863.82  4427.4 1860.86  4511.7 1858.03  4575.7 1858.08  4866.7 1850.83
  4923.3 1853.95  4979.9 1847.23  4996.9 1842.53  5001.2 1838.84  5002.2 1838.34
  5045.9 1838.84  5051.6 1841.32  5085.3 1841.55  5141.6  1843.2  5147.3 1878.61
  5163.2 1885.28  5168.9 1893.32  5184.8 1899.53  5190.5 1909.09  5200.6 1911.79
  5206.4 1917.78  5249.5 1933.68  5264.2 1934.83    5346 1939.11  5397.1 1938.66
#Mann= 10 ,-1 , 0
  3862.6      .1       0    4125     .07       0  4341.8    .035       0
  4427.4     .07       0  4511.7    .035       0  4575.7     .07       0
  5001.2     .05       0  5045.9     .07       0  5085.3      .1       0
  5264.2     .07       0
Bank Sta=5001.2,5045.9
XS Rating Curve= 0 ,0
Exp/Cntr=0.3,0.1

Type RM Length L Ch R = 1 ,2260    ,534,534,534
BEGIN DESCRIPTION:
Bear Creek 2 3.0
END DESCRIPTION:
XS GIS Cut Line= 3
      1836625.02     13934925.02        1835825.       13934125.
      1835475.01     13933875.01
#Sta/Elev= 30
  3873.1 1994.66  3943.8 1968.98  4099.4 1898.36  4198.4 1864.36  4226.7 1858.31
  4291.6 1855.65  4433.3 1854.75  4527.5 1851.92  4577.1 1852.13  4720.8 1849.53
  4806.5 1849.93  4891.4    1839  4913.5 1839.68  4918.2  1839.6  4939.7 1838.64
  4940.7 1838.14  4984.4 1838.64  5026.6 1839.89  5032.8 1844.41  5062.3 1851.05
  5068.4 1855.43    5077 1854.63  5083.1 1859.44  5097.9 1857.26    5104 1873.91
  5112.6 1885.85  5118.8 1913.91  5176.5 1924.34  5305.1 1927.89  5434.6 1930.67
#Mann= 11 ,-1 , 0
  3873.1      .1       0  4291.6     .07       0  4433.3    .035       0
  4527.5      .1       0  4577.1     .07       0  4720.8      .1       0
  4913.5     .07       0  4918.2      .1       0  4939.7     .05       0
  4984.4      .1       0  5305.1     .07       0
Bank Sta=4939.7,4984.4
XS Rating Curve= 0 ,0
Exp/Cntr=0.3,0.1

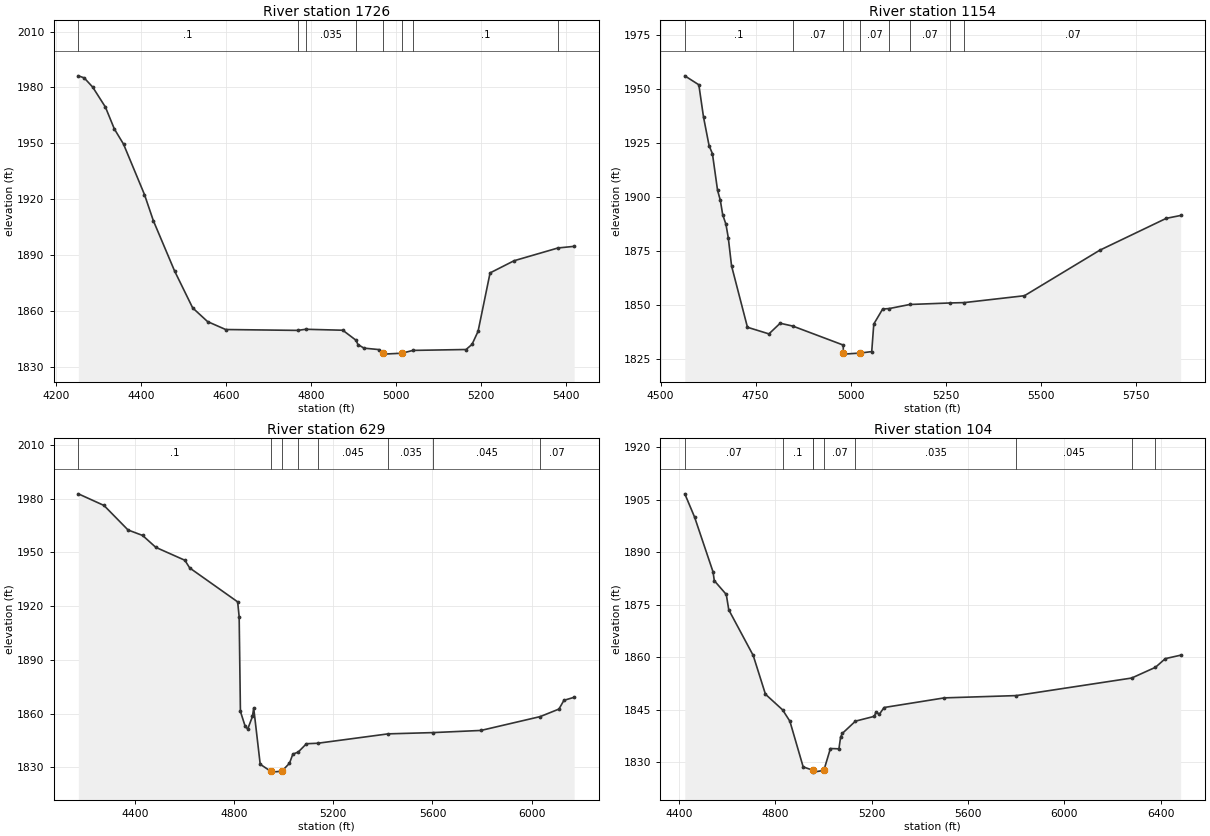
Type RM Length L Ch R = 1 ,1726    ,572,572,572
BEGIN DESCRIPTION:
Bear Creek 2 2.0
END DESCRIPTION:
XS GIS Cut Line= 3
      1836824.99     13934724.99        1836325.       13934175.
      1836024.97     13933874.97
#Sta/Elev= 30
  4252.5 1986.25  4266.3 1985.15  4286.3  1980.2  4316.3 1969.45  4337.3 1957.72
  4358.9 1949.57  4408.2  1922.5  4429.2 1908.41  4479.2  1881.4  4521.8 1861.57
  4556.9 1854.22  4599.5 1849.97  4769.2  1849.5  4787.8  1850.1  4875.2 1849.59
  4906.1 1844.26    4911  1841.9  4925.2 1839.97  4960.3 1839.19  4970.1 1837.25
  4971.1 1836.75  5014.8 1837.25  5040.4 1838.75  5165.5 1839.23  5179.6 1841.99
  5193.8 1848.98  5222.1 1880.38  5278.6 1886.92  5382.1 1893.78  5420.1 1894.65
#Mann= 8 ,-1 , 0
  4252.5      .1       0  4769.2     .07       0  4787.8    .035       0
  4906.1     .07       0  4970.1     .05       0  5014.8     .07       0
  5040.4      .1       0  5382.1     .07       0
Bank Sta=4970.1,5014.8
XS Rating Curve= 0 ,0
Exp/Cntr=0.3,0.1

Type RM Length L Ch R = 1 ,1154    ,525,525,525
BEGIN DESCRIPTION:
Bear Creek 2 1.0
END DESCRIPTION:
XS GIS Cut Line= 3
      1837075.03     13934325.04        1836825.       13933975.
      1836024.98     13933624.99
#Sta/Elev= 30
  4563.7 1956.15  4600.6    1952  4612.9 1937.06  4627.6 1923.77  4636.3 1920.14
  4649.8 1903.18  4657.1 1898.51  4663.3 1891.89  4671.9  1887.4    4678 1881.21
  4686.6 1868.17  4728.4 1839.75  4784.9 1836.68  4814.4 1841.61  4847.7 1840.29
  4980.3  1831.5  4980.4 1827.81  4981.4 1827.31  5025.2 1827.81  5055.1 1828.49
  5060.5 1841.24  5083.9 1848.21  5100.9  1848.4  5155.1 1850.29  5261.2    1851
  5298.1 1851.16  5456.6 1854.35  5654.6 1875.42  5829.3 1890.17  5867.1  1891.5
#Mann= 8 ,-1 , 0
  4563.7      .1       0  4847.7     .07       0  4980.4     .05       0
  5025.2     .07       0  5100.9    .035       0  5155.1     .07       0
  5261.2    .035       0  5298.1     .07       0
Bank Sta=4980.4,5025.2
XS Rating Curve= 0 ,0
Exp/Cntr=0.3,0.1

Type RM Length L Ch R = 1 ,629     ,525,525,525
BEGIN DESCRIPTION:
Bear Creek 2 0.0
END DESCRIPTION:
XS GIS Cut Line= 4
      1837455.79     13934616.71      1837324.28     13933891.22
      1837231.91     13933647.99      1836244.36     13933486.83
#Sta/Elev= 30
  4172.8 1982.71  4276.2 1976.22  4373.1 1962.53  4431.6 1959.49  4485.1 1952.83
  4602.1 1945.63  4621.7 1941.33  4814.8 1922.41  4820.9 1914.12    4826 1861.24
  4845.3  1852.9  4855.5 1851.42  4874.4 1858.43  4879.5 1863.17  4905.7 1831.77
  4947.9 1827.87  4948.9 1827.37  4992.7 1827.87  5023.7 1832.32  5037.3 1837.43
  5058.7 1838.55  5092.2 1843.23  5137.7 1843.49  5421.2 1848.73  5601.3 1849.43
  5795.4 1850.64  6033.9 1858.36  6109.5 1862.56  6129.7 1867.45  6170.9 1869.14
#Mann= 8 ,-1 , 0
  4172.8      .1       0  4947.9     .05       0  4992.7      .1       0
  5058.7    .035       0  5137.7    .045       0  5421.2    .035       0
  5601.3    .045       0  6033.9     .07       0
Bank Sta=4947.9,4992.7
XS Rating Curve= 0 ,0
Exp/Cntr=0.3,0.1

Type RM Length L Ch R = 1 ,104     ,0,0,0
BEGIN DESCRIPTION:
Bear Creek 2 0.1
END DESCRIPTION:
XS GIS Cut Line= 4
      1837650.02     13933994.92      1837726.41     13933550.48
      1837528.49     13933362.98      1836195.14     13933307.42
#Sta/Elev= 30
  4424.3 1906.66  4464.8 1900.04  4541.6 1884.37  4546.7 1881.88  4596.5 1877.94
  4606.9 1873.54  4708.3 1860.53  4759.1 1849.47  4830.3 1845.01  4860.5 1841.77
  4915.6 1828.74  4956.2 1827.77  4956.7 1827.74  4957.7 1827.24  5001.5 1827.74
  5028.7 1833.98  5064.1 1833.89    5071 1837.23  5078.2 1838.29  5132.7 1841.79
  5211.4 1843.17  5217.9 1844.48  5231.5 1843.72  5251.5 1845.68  5501.7 1848.43
  5800.2 1849.08  6279.2 1854.09  6377.8 1857.15  6418.9 1859.63  6482.4 1860.61
#Mann= 9 ,-1 , 0
  4424.3     .07       0  4830.3      .1       0  4956.2     .07       0
  4956.7     .05       0  5001.5     .07       0  5132.7    .035       0
  5800.2    .045       0  6279.2    .035       0  6377.8     .07       0
Bank Sta=4956.7,5001.5
XS Rating Curve= 0 ,0
Exp/Cntr=0.3,0.1

Chan Stop Cuts=-1
Use User Specified Reach Order=0
Composite Channel Slope=5