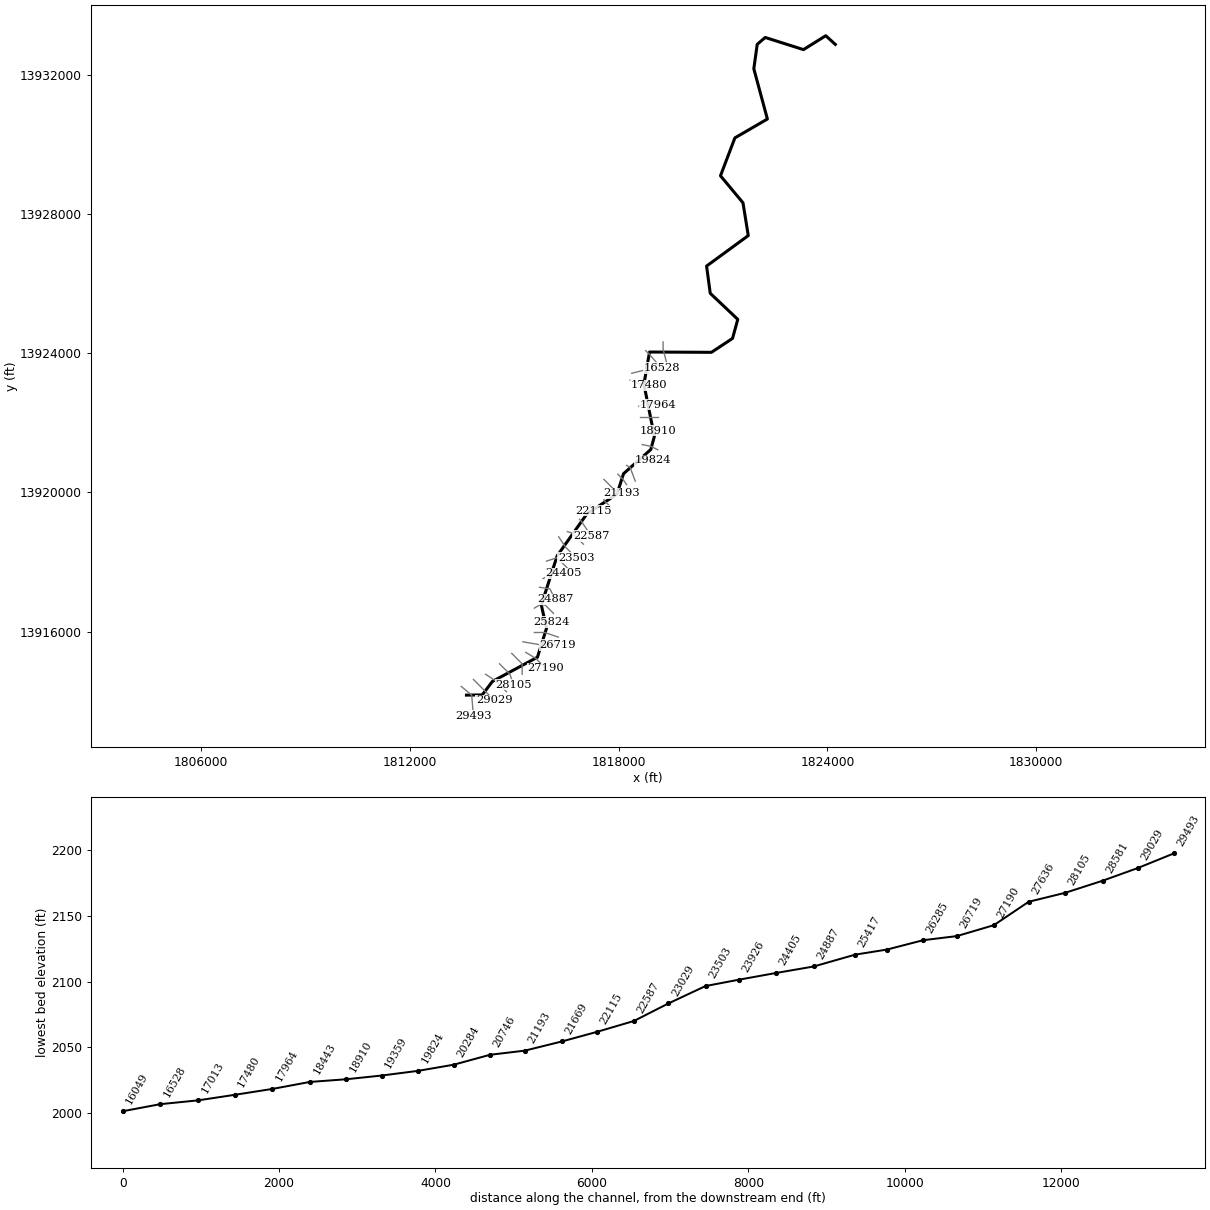
--- Bee Caves Creek.prj (project) ---

Proj Title=Bee Caves Creek Base Level Engineering
Current Plan=p01
Default Exp/Contr=0.3,0.1
English Units
Geom File=g01
Flow File=f01
Plan File=p01
BEGIN DESCRIPTION:
Bee Caves Creek
END DESCRIPTION:

--- Bee Caves Creek.p01 (plan) ---

Plan Title=Multiple Run
Short Identifier=Multiple
Geom File=g01
Flow File=f01
Subcritical Flow
K Sum by GR= 0
Std Step Tol= 0.01
Critical Tol= 0.01
Num of Std Step Trials= 20
Max Error Tol= 0.3
Flow Tol Ratio= 0.001
Split Flow NTrial= 30
Split Flow Tol= 0.02
Split Flow Ratio= 0.02
Log Output Level= 0
Friction Slope Method= 1
Unsteady Friction Slope Method= 2
Unsteady Bridges Friction Slope Method= 1
Parabolic Critical Depth
Global Vel Dist=  1 , 1 , 1
Global Log Level= 0
CheckData=True
Encroach Param= -1, 0, 0, 0
BEGIN DESCRIPTION:
Multiple Run
END DESCRIPTION:

--- Bee Caves Creek.f01 (steady flow) ---

Flow Title=Multiple
Number of Profiles=7
Profile Names=10-year,25-year,50-year,1pct_min,100-year,1pct_plu,500-year
River Rch & RM= Bee Caves Creek,Reach-1,29493
     287     452     597     384     765    1527    1237
River Rch & RM= Bee Caves Creek,Reach-1,27636
    1318    2296    3242    2212    4413    8805    8087
River Rch & RM= Bee Caves Creek,Reach-1,21193
    1954    3468    4960    3420    6824   13615   12787
River Rch & RM= Bee Caves Creek,Reach-1,17480
    2351    4205    6044    4185    8350   16660   15779
River Rch & RM= Bee Caves Creek,Reach-1,13758
    3443    6246    9063    6325   12620   25180   24238
River Rch & RM= Bee Caves Creek,Reach-1,5545
    3467    6282    9106    6348   12666   25271   24272
Boundary for River Rch & Prof#=Bee Caves Creek,Reach-1,1
Up Type=0
Dn Type=3
Dn Slope=0.005
Boundary for River Rch & Prof#=Bee Caves Creek,Reach-1,2
Up Type=0
Dn Type=3
Dn Slope=0.005
Boundary for River Rch & Prof#=Bee Caves Creek,Reach-1,3
Up Type=0
Dn Type=3
Dn Slope=0.005
Boundary for River Rch & Prof#=Bee Caves Creek,Reach-1,4
Up Type=0
Dn Type=3
Dn Slope=0.005
Boundary for River Rch & Prof#=Bee Caves Creek,Reach-1,5
Up Type=0
Dn Type=3
Dn Slope=0.005
Boundary for River Rch & Prof#=Bee Caves Creek,Reach-1,6
Up Type=0
Dn Type=3
Dn Slope=0.005
Boundary for River Rch & Prof#=Bee Caves Creek,Reach-1,7
Up Type=0
Dn Type=3
Dn Slope=0.005

--- Bee Caves Creek.g01 (geometry) ---

Geom Title=Existing Conditions

River Reach=Bee Caves Creek,Reach-1
Reach XY= 30
      1813625.00     13914175.00      1814077.74     13914180.34
      1814368.83     13914567.14      1815664.35     13915265.00
      1815925.30     13916095.18      1815776.20     13916764.50
      1816230.83     13918177.30      1817091.65     13919391.67
      1817948.71     13919948.18      1818138.54     13920538.38
      1818921.85     13921233.32      1819024.49     13921609.78
      1818724.57     13923109.82      1818885.61     13924035.06
      1820664.50     13924026.20      1821271.24     13924426.56
      1821421.47     13924973.53      1820630.54     13925722.58
      1820524.96     13926505.02      1821722.94     13927380.85
      1821571.25     13928323.45      1820924.76     13929100.08
      1821338.40     13930188.30      1822272.84     13930730.97
      1821882.56     13932175.00      1821980.46     13932877.45
      1822209.58     13933074.97      1823309.78     13932725.49
      1823950.00     13933125.42      1824225.00     13932875.00

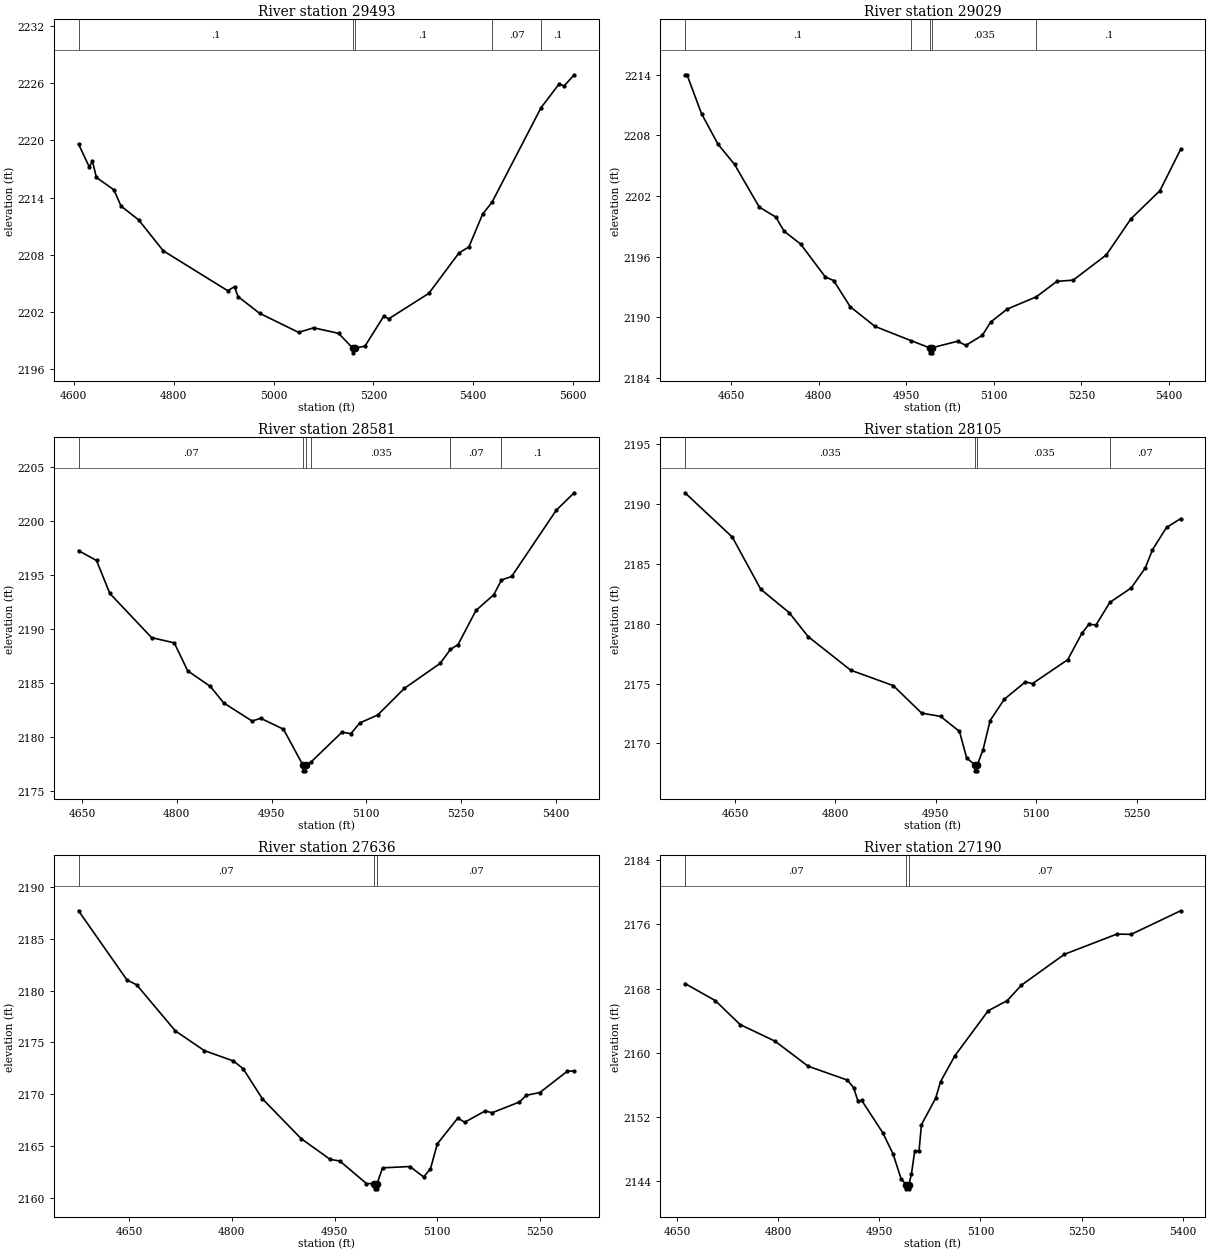
Type RM Length L Ch R = 1,29493,464,464,464
BEGIN DESCRIPTION:
Bee Caves Creek 64.0
END DESCRIPTION:
XS GIS Cut Line= 3
      1813475.02     13914424.98      1813775.00     13914175.00
      1813825.00     13913574.97
#Sta/Elev= 30
  4609.5 2219.62  4631.0 2217.23  4637.5 2217.80  4645.3 2216.11  4680.4 2214.81
  4694.7 2213.10  4729.9 2211.65  4779.3 2208.40  4908.2 2204.21  4921.9 2204.63
  4929.0 2203.59  4972.0 2201.84  5050.2 2199.83  5080.3 2200.31  5130.4 2199.73
  5158.5 2198.18  5158.8 2197.68  5162.5 2198.18  5183.1 2198.38  5220.8 2201.53
  5230.8 2201.26  5311.1 2203.93  5371.3 2208.17  5391.3 2208.81  5418.9 2212.27
  5437.4 2213.49  5535.9 2223.45  5572.0 2225.94  5582.0 2225.72  5602.1 2226.90
#Mann=5,-1,0
  4609.5     0.1       0  5158.5    0.05       0  5162.5     0.1       0
  5437.4    0.07       0  5535.9     0.1       0
Bank Sta=5158.5,5162.5
Exp/Cntr=0.3,0.1

Type RM Length L Ch R = 1,29029,448,448,448
BEGIN DESCRIPTION:
Bee Caves Creek 63.0
END DESCRIPTION:
XS GIS Cut Line= 3
      1813825.02     13914624.98      1814125.00     13914325.00
      1814425.00     13914025.00
#Sta/Elev= 30
  4571.4 2214.01  4574.9 2214.01  4599.7 2210.16  4627.9 2207.14  4656.2 2205.14
  4698.6 2200.91  4726.9 2199.92  4741.1 2198.52  4769.4 2197.25  4811.8 2193.98
  4825.9 2193.64  4854.2 2191.05  4896.6 2189.10  4958.7 2187.68  4990.1 2186.98
  4990.3 2186.48  4993.8 2186.48  4994.1 2186.98  5038.1 2187.63  5052.2 2187.22
  5080.5 2188.22  5094.6 2189.52  5122.9 2190.81  5173.0 2192.03  5207.8 2193.55
  5236.0 2193.68  5292.6 2196.17  5335.0 2199.76  5384.5 2202.54  5419.9 2206.63
#Mann=5,-1,0
  4571.4     0.1       0  4958.7   0.035       0  4990.1   0.035       0
  4994.1   0.035       0  5173.0     0.1       0
Bank Sta=4990.1,4994.1
Exp/Cntr=0.3,0.1

Type RM Length L Ch R = 1,28581,476,476,476
BEGIN DESCRIPTION:
Bee Caves Creek 62.0
END DESCRIPTION:
XS GIS Cut Line= 3
      1814175.00     13914775.00      1814475.00     13914575.00
      1814774.98     13914275.02
#Sta/Elev= 30
  4644.4 2197.23  4672.9 2196.32  4694.0 2193.27  4760.1 2189.19  4796.1 2188.70
  4817.2 2186.12  4853.2 2184.67  4874.3 2183.15  4919.3 2181.47  4932.8 2181.73
  4968.9 2180.72  5000.0 2177.37  5000.2 2176.87  5003.7 2176.87  5004.0 2177.37
  5012.1 2177.66  5061.5 2180.44  5075.7 2180.31  5089.8 2181.30  5118.1 2182.03
  5160.5 2184.50  5217.1 2186.81  5233.2 2188.09  5245.4 2188.55  5273.7 2191.70
  5301.9 2193.15  5314.1 2194.52  5330.2 2194.84  5400.9 2200.97  5429.2 2202.58
#Mann=6,-1,0
  4644.4    0.07       0  5000.0    0.05       0  5004.0    0.07       0
  5012.1   0.035       0  5233.2    0.07       0  5314.1     0.1       0
Bank Sta=5000,5004
Exp/Cntr=0.3,0.1

Type RM Length L Ch R = 1,28105,469,469,469
BEGIN DESCRIPTION:
Bee Caves Creek 61.0
END DESCRIPTION:
XS GIS Cut Line= 3
      1814574.98     13915075.02      1814875.00     13914775.00
      1814974.99     13914475.02
#Sta/Elev= 30
  4575.4 2190.94  4646.1 2187.24  4688.6 2182.88  4731.0 2180.93  4759.3 2178.93
  4822.9 2176.12  4886.6 2174.83  4929.0 2172.53  4957.3 2172.26  4985.5 2171.00
  4996.2 2168.79  5008.2 2168.21  5008.5 2167.71  5012.0 2167.71  5012.2 2168.21
  5020.8 2169.49  5031.3 2171.91  5052.4 2173.69  5084.0 2175.14  5094.6 2175.00
  5147.3 2177.00  5168.3 2179.19  5178.9 2179.96  5189.4 2179.89  5210.1 2181.78
  5242.1 2182.99  5263.2 2184.67  5273.8 2186.18  5294.8 2188.04  5315.9 2188.78
#Mann=4,-1,0
  4575.4   0.035       0  5008.2   0.035       0  5012.2   0.035       0
  5210.1    0.07       0
Bank Sta=5008.2,5012.2
Exp/Cntr=0.3,0.1

Type RM Length L Ch R = 1,27636,446,446,446
BEGIN DESCRIPTION:
Bee Caves Creek 60.0
END DESCRIPTION:
XS GIS Cut Line= 3
      1814924.97     13915375.03      1815225.00     13915075.00
      1815225.00     13914775.01
#Sta/Elev= 30
  4575.9 2187.74  4646.7 2181.05  4660.8 2180.58  4717.4 2176.12  4759.8 2174.21
  4802.2 2173.21  4816.4 2172.47  4844.6 2169.55  4901.2 2165.70  4943.6 2163.69
  4957.8 2163.53  4996.7 2161.35  5008.2 2161.34  5008.5 2160.84  5012.0 2160.84
  5012.2 2161.34  5020.2 2162.87  5060.2 2163.00  5080.2 2161.99  5090.2 2162.77
  5100.2 2165.19  5130.2 2167.69  5140.2 2167.28  5170.2 2168.38  5180.2 2168.20
  5220.2 2169.24  5230.2 2169.89  5250.2 2170.16  5290.2 2172.22  5300.2 2172.24
#Mann=3,-1,0
  4575.9    0.07       0  5008.2    0.05       0  5012.2    0.07       0
Bank Sta=5008.2,5012.2
Exp/Cntr=0.3,0.1

Type RM Length L Ch R = 1,27190,471,471,471
BEGIN DESCRIPTION:
Bee Caves Creek 59.0
END DESCRIPTION:
XS GIS Cut Line= 3
      1815330.65     13915402.71      1815625.00     13915225.00
      1815898.31     13914944.46
#Sta/Elev= 30
  4661.6 2168.63  4706.6 2166.50  4743.4 2163.51  4795.2 2161.44  4844.4 2158.31
  4902.6 2156.58  4912.0 2155.61  4918.1 2153.99  4923.9 2154.04  4955.0 2150.02
  4970.4 2147.36  4982.2 2144.29  4989.8 2143.51  4990.1 2143.01  4993.6 2143.01
  4993.8 2143.51  4997.7 2144.88  5002.5 2147.72  5008.9 2147.72  5012.5 2151.02
  5033.6 2154.32  5040.8 2156.38  5061.9 2159.59  5111.5 2165.23  5139.8 2166.50
  5160.9 2168.43  5224.7 2172.28  5302.4 2174.80  5323.7 2174.77  5397.1 2177.71
#Mann=3,-1,0
  4661.6    0.07       0  4989.8    0.05       0  4993.8    0.07       0
Bank Sta=4989.8,4993.8
Exp/Cntr=0.3,0.1

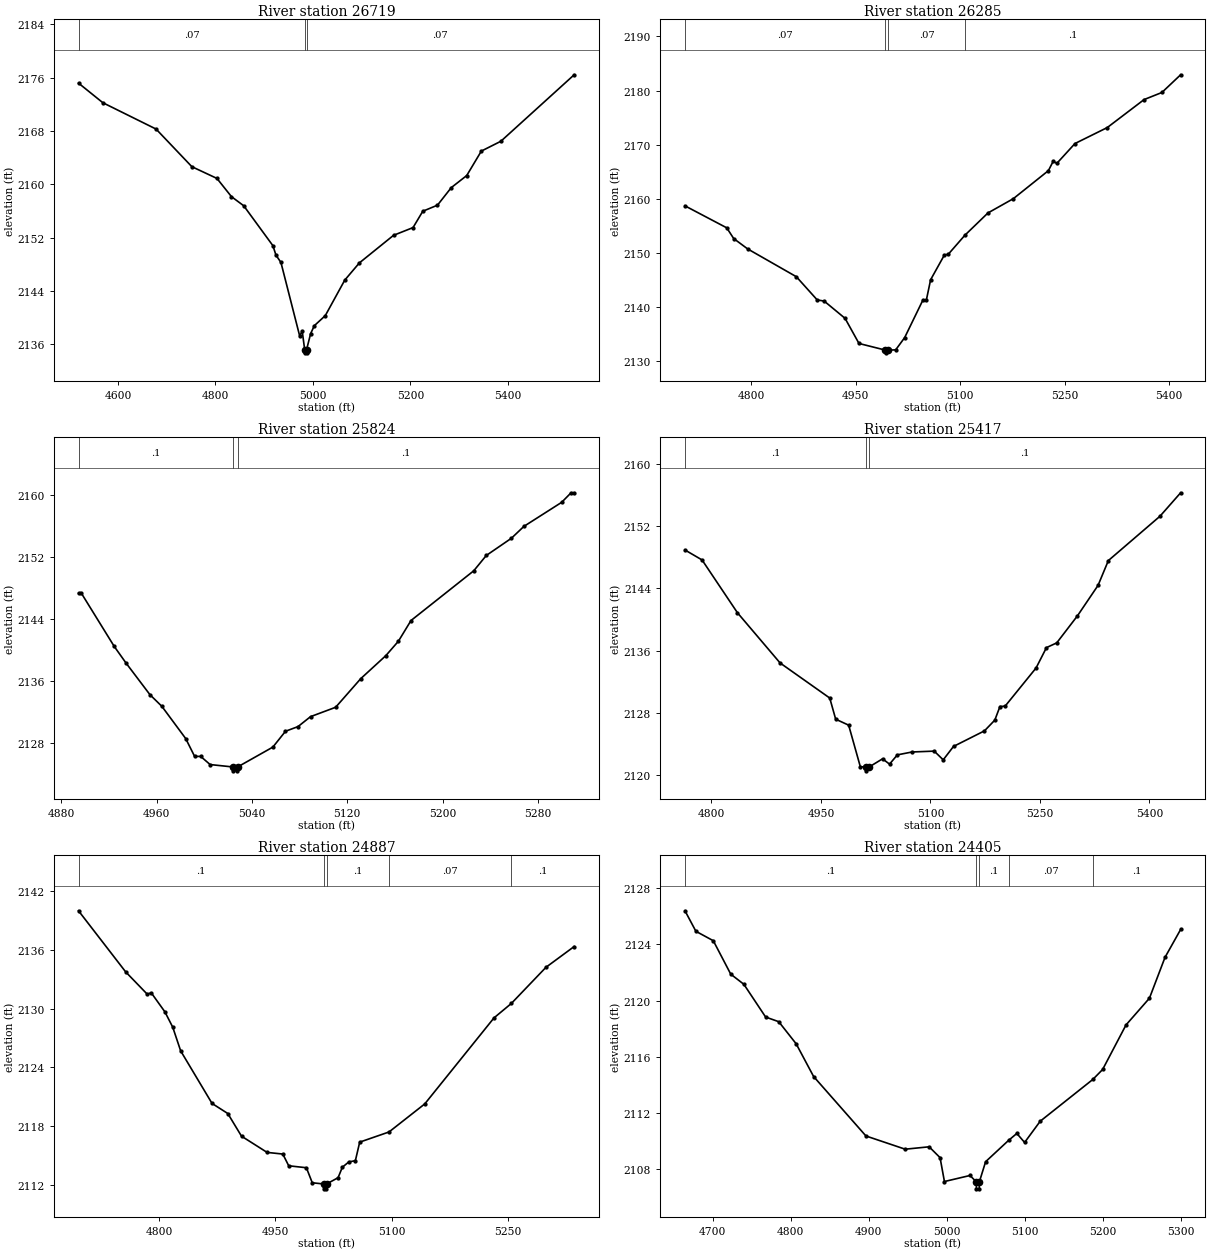
Type RM Length L Ch R = 1,26719,434,434,434
BEGIN DESCRIPTION:
Bee Caves Creek 58.0
END DESCRIPTION:
XS GIS Cut Line= 3
      1815245.82     13915707.41      1815725.00     13915625.00
      1816255.40     13915615.59
#Sta/Elev= 30
  4519.1 2175.16  4569.0 2172.22  4678.2 2168.27  4751.6 2162.63  4803.1 2160.87
  4832.8 2158.14  4858.0 2156.77  4917.9 2150.78  4924.1 2149.37  4934.3 2148.28
  4972.8 2137.24  4977.9 2137.99  4983.0 2135.22  4983.3 2134.72  4986.8 2134.72
  4987.0 2135.22  4995.2 2137.59  5002.8 2138.79  5025.3 2140.30  5065.3 2145.63
  5095.3 2148.21  5165.3 2152.34  5205.3 2153.50  5225.3 2155.95  5255.4 2156.86
  5283.7 2159.49  5315.4 2161.30  5345.4 2164.97  5385.4 2166.44  5535.8 2176.41
#Mann=3,-1,0
  4519.1    0.07       0  4983.0    0.05       0  4987.0    0.07       0
Bank Sta=4983,4987
Exp/Cntr=0.3,0.1

Type RM Length L Ch R = 1,26285,461,461,461
BEGIN DESCRIPTION:
Bee Caves Creek 57.0
END DESCRIPTION:
XS GIS Cut Line= 3
      1815574.97     13915975.00      1815875.00     13915975.00
      1816264.69     13915841.02
#Sta/Elev= 30
  4704.7 2158.71  4764.7 2154.65  4774.7 2152.67  4794.7 2150.76  4864.7 2145.62
  4894.7 2141.33  4904.7 2141.12  4934.7 2137.93  4954.7 2133.29  4992.7 2132.06
  4993.0 2131.56  4996.7 2132.06  5007.4 2132.11  5020.3 2134.37  5046.3 2141.25
  5051.6 2141.38  5057.6 2145.06  5077.5 2149.66  5082.8 2149.74  5106.9 2153.29
  5140.0 2157.40  5176.5 2160.04  5226.8 2165.21  5233.7 2166.94  5239.0 2166.56
  5265.0 2170.22  5311.4 2173.17  5364.3 2178.34  5389.9 2179.65  5416.8 2182.92
#Mann=4,-1,0
  4704.7    0.07       0  4992.7    0.05       0  4996.7    0.07       0
  5106.9     0.1       0
Bank Sta=4992.7,4996.7
Exp/Cntr=0.3,0.1

Type RM Length L Ch R = 1,25824,407,407,407
BEGIN DESCRIPTION:
Bee Caves Creek 56.0
END DESCRIPTION:
XS GIS Cut Line= 3
      1815675.03     13916375.00      1815775.00     13916375.00
      1816075.01     13916275.00
#Sta/Elev= 30
  4894.3 2147.31  4896.8 2147.31  4924.3 2140.48  4934.3 2138.32  4954.3 2134.26
  4964.3 2132.76  4984.3 2128.61  4991.8 2126.31  4996.9 2126.31  5004.8 2125.26
  5023.9 2124.95  5024.1 2124.45  5027.6 2124.45  5027.9 2124.95  5057.5 2127.51
  5068.1 2129.55  5078.6 2130.15  5089.1 2131.43  5110.2 2132.64  5131.3 2136.33
  5152.4 2139.30  5162.9 2141.15  5173.5 2143.82  5226.2 2150.23  5236.7 2152.20
  5257.8 2154.42  5268.3 2155.95  5300.0 2159.05  5307.9 2160.28  5310.5 2160.28
#Mann=3,-1,0
  4894.3     0.1       0  5023.9    0.05       0  5027.9     0.1       0
Bank Sta=5023.9,5027.9
Exp/Cntr=0.3,0.1

Type RM Length L Ch R = 1,25417,530,530,530
BEGIN DESCRIPTION:
Bee Caves Creek 55.0
END DESCRIPTION:
XS GIS Cut Line= 4
      1815574.97     13916674.98      1815753.96     13916782.37
      1815890.06     13916759.94      1816124.98     13916525.02
#Sta/Elev= 30
  4763.8 2148.92  4787.2 2147.64  4835.7 2140.86  4894.1 2134.42  4962.1 2129.92
  4970.2 2127.21  4988.0 2126.44  5004.0 2121.10  5012.1 2121.08  5012.4 2120.58
  5016.1 2121.08  5034.4 2122.12  5044.0 2121.44  5054.7 2122.63  5074.9 2123.00
  5105.2 2123.11  5117.5 2121.99  5131.6 2123.71  5174.0 2125.71  5188.2 2127.09
  5195.2 2128.83  5202.3 2128.88  5244.7 2133.78  5258.9 2136.39  5273.0 2137.00
  5301.3 2140.46  5329.6 2144.38  5343.7 2147.56  5414.4 2153.25  5442.7 2156.26
#Mann=3,-1,0
  4763.8     0.1       0  5012.1    0.05       0  5016.1     0.1       0
Bank Sta=5012.1,5016.1
Exp/Cntr=0.3,0.1

Type RM Length L Ch R = 1,24887,482,482,482
BEGIN DESCRIPTION:
Bee Caves Creek 54.0
END DESCRIPTION:
XS GIS Cut Line= 3
      1815725.02     13917275.00      1816025.00     13917225.00
      1816174.99     13916925.02
#Sta/Elev= 30
  4695.9 2140.02  4756.7 2133.77  4784.6 2131.48  4789.7 2131.63  4807.4 2129.67
  4817.5 2128.10  4827.7 2125.68  4868.2 2120.30  4888.5 2119.27  4906.2 2116.95
  4939.2 2115.29  4959.5 2115.12  4967.1 2113.92  4989.9 2113.72  4997.5 2112.18
  5012.0 2112.06  5012.2 2111.56  5015.7 2111.56  5016.0 2112.06  5030.8 2112.70
  5036.3 2113.77  5044.7 2114.32  5053.1 2114.44  5058.7 2116.34  5096.5 2117.38
  5142.6 2120.25  5232.0 2129.06  5254.3 2130.53  5299.1 2134.24  5335.4 2136.36
#Mann=5,-1,0
  4695.9     0.1       0  5012.0    0.05       0  5016.0     0.1       0
  5096.5    0.07       0  5254.3     0.1       0
Bank Sta=5012,5016
Exp/Cntr=0.3,0.1

Type RM Length L Ch R = 1,24405,479,479,479
BEGIN DESCRIPTION:
Bee Caves Creek 53.0
END DESCRIPTION:
XS GIS Cut Line= 3
      1815825.01     13917525.00      1816125.00     13917675.00
      1816425.00     13917675.00
#Sta/Elev= 30
  4664.6 2126.39  4678.6 2124.93  4700.9 2124.26  4723.3 2121.88  4740.1 2121.16
  4768.0 2118.83  4784.8 2118.50  4807.1 2116.93  4829.5 2114.60  4896.6 2110.37
  4946.9 2109.43  4977.6 2109.60  4991.6 2108.83  4997.2 2107.13  5030.0 2107.56
  5038.0 2107.11  5038.3 2106.61  5041.8 2106.61  5042.0 2107.11  5050.0 2108.54
  5079.5 2110.06  5090.0 2110.55  5100.0 2109.91  5120.0 2111.42  5187.4 2114.39
  5200.0 2115.10  5230.0 2118.27  5260.0 2120.17  5280.0 2123.08  5300.0 2125.06
#Mann=5,-1,0
  4664.6     0.1       0  5038.0    0.05       0  5042.0     0.1       0
  5079.5    0.07       0  5187.4     0.1       0
Bank Sta=5038,5042
Exp/Cntr=0.3,0.1

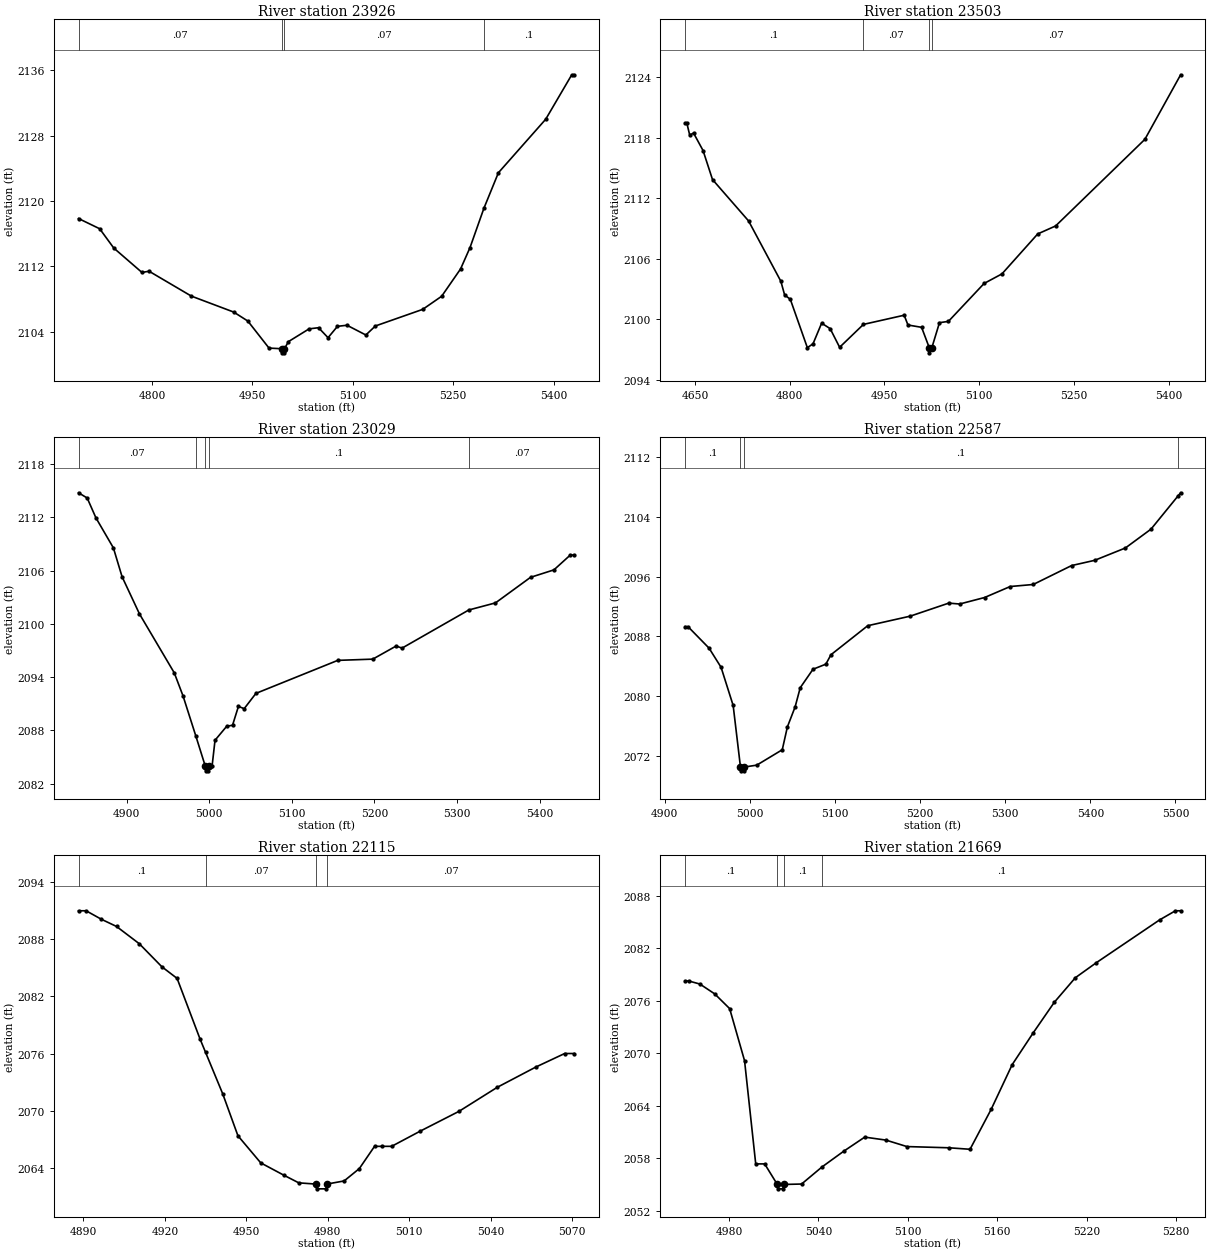
Type RM Length L Ch R = 1,23926,423,423,423
BEGIN DESCRIPTION:
Bee Caves Creek 52.0
END DESCRIPTION:
XS GIS Cut Line= 3
      1815925.03     13918025.01      1816225.00     13918125.00
      1816525.03     13917824.97
#Sta/Elev= 30
  4690.2 2117.86  4721.8 2116.61  4742.9 2114.25  4785.0 2111.27  4795.6 2111.42
  4858.8 2108.38  4922.1 2106.43  4943.2 2105.33  4974.8 2102.03  4993.9 2101.95
  4994.1 2101.45  4997.6 2101.45  4997.9 2101.95  5003.8 2102.82  5034.7 2104.38
  5048.8 2104.52  5063.0 2103.30  5077.1 2104.69  5091.3 2104.82  5119.5 2103.63
  5133.7 2104.73  5204.4 2106.76  5232.7 2108.36  5261.0 2111.70  5275.1 2114.31
  5295.9 2119.12  5317.5 2123.45  5388.2 2129.99  5427.1 2135.42  5430.7 2135.42
#Mann=4,-1,0
  4690.2    0.07       0  4993.9    0.05       0  4997.9    0.07       0
  5295.9     0.1       0
Bank Sta=4993.9,4997.9
Exp/Cntr=0.3,0.1

Type RM Length L Ch R = 1,23503,474,474,474
BEGIN DESCRIPTION:
Bee Caves Creek 51.0
END DESCRIPTION:
XS GIS Cut Line= 3
      1816274.98     13918725.03      1816475.00     13918425.00
      1816775.03     13918124.97
#Sta/Elev= 30
  4634.3 2119.42  4637.3 2119.42  4641.8 2118.25  4647.9 2118.45  4662.9 2116.72
  4677.9 2113.84  4735.0 2109.74  4786.1 2103.76  4792.1 2102.40  4801.1 2101.97
  4828.1 2097.17  4837.1 2097.56  4850.7 2099.60  4864.2 2099.06  4879.2 2097.21
  4916.9 2099.48  4981.4 2100.39  4987.4 2099.42  5009.0 2099.19  5021.2 2097.16
  5021.4 2096.66  5025.2 2097.16  5037.3 2099.65  5051.5 2099.78  5108.0 2103.54
  5136.3 2104.49  5192.9 2108.45  5221.2 2109.24  5362.6 2117.83  5419.2 2124.23
#Mann=4,-1,0
  4634.3     0.1       0  4916.9    0.07       0  5021.2    0.05       0
  5025.2    0.07       0
Bank Sta=5021.2,5025.2
Exp/Cntr=0.3,0.1

Type RM Length L Ch R = 1,23029,442,442,442
BEGIN DESCRIPTION:
Bee Caves Creek 50.0
END DESCRIPTION:
XS GIS Cut Line= 3
      1816525.00     13918875.00      1816675.00     13918825.00
      1816986.63     13918511.99
#Sta/Elev= 30
  4841.9 2114.77  4852.4 2114.18  4863.0 2111.94  4884.1 2108.56  4894.6 2105.31
  4915.7 2101.11  4957.8 2094.47  4968.4 2091.87  4983.9 2087.35  4995.4 2083.93
  4995.6 2083.43  4999.1 2083.43  4999.4 2083.93  5003.5 2083.93  5007.1 2086.88
  5021.2 2088.45  5028.3 2088.57  5035.4 2090.69  5042.4 2090.44  5056.6 2092.16
  5155.6 2095.88  5198.0 2096.02  5226.3 2097.50  5233.4 2097.26  5314.2 2101.56
  5346.5 2102.36  5388.9 2105.24  5417.2 2106.08  5437.0 2107.75  5441.7 2107.75
#Mann=5,-1,0
  4841.9    0.07       0  4983.9     0.1       0  4995.4    0.05       0
  4999.4     0.1       0  5314.2    0.07       0
Bank Sta=4995.4,4999.4
Exp/Cntr=0.3,0.1

Type RM Length L Ch R = 1,22587,472,472,472
BEGIN DESCRIPTION:
Bee Caves Creek 49.0
END DESCRIPTION:
XS GIS Cut Line= 3
      1816874.99     13919225.01      1816925.00     13919175.00
      1817207.69     13918748.63
#Sta/Elev= 30
  4923.8 2089.31  4927.4 2089.31  4952.1 2086.44  4966.2 2083.88  4980.4 2078.78
  4989.0 2070.54  4989.2 2070.04  4992.7 2070.04  4993.0 2070.54  5008.1 2070.80
  5038.1 2072.86  5044.1 2075.91  5053.2 2078.59  5059.2 2081.15  5074.2 2083.62
  5089.3 2084.30  5095.3 2085.56  5138.5 2089.44  5188.5 2090.72  5233.7 2092.46
  5246.5 2092.34  5275.8 2093.21  5305.9 2094.68  5332.9 2094.95  5378.0 2097.48
  5405.1 2098.18  5441.2 2099.83  5471.3 2102.35  5503.2 2106.81  5506.1 2107.21
#Mann=4,-1,0
  4923.8     0.1       0  4989.0    0.05       0  4993.0     0.1       0
  5503.2    0.07       0
Bank Sta=4989,4993
Exp/Cntr=0.3,0.1

Type RM Length L Ch R = 1,22115,446,446,446
BEGIN DESCRIPTION:
Bee Caves Creek 48.0
END DESCRIPTION:
XS GIS Cut Line= 3
      1817175.00     13919625.00      1817225.00     13919525.00
      1817274.99     13919475.01
#Sta/Elev= 29
  4888.2 2091.01  4891.0 2091.01  4896.6 2090.12  4902.2 2089.36  4910.6 2087.54
  4918.9 2085.12  4924.5 2083.90  4932.9 2077.56  4935.0 2076.11  4941.3 2071.76
  4946.9 2067.35  4955.3 2064.50  4963.7 2063.22  4969.3 2062.40  4975.6 2062.27
  4975.9 2061.77  4979.4 2061.77  4979.6 2062.27  4986.0 2062.60  4991.6 2063.90
  4997.2 2066.24  5000.0 2066.24  5003.5 2066.24  5014.1 2067.85  5028.3 2069.92
  5042.4 2072.45  5056.6 2074.58  5067.2 2076.00  5070.7 2076.00
#Mann=4,-1,0
  4888.2     0.1       0  4935.0    0.07       0  4975.6    0.05       0
  4979.6    0.07       0
Bank Sta=4975.6,4979.6
Exp/Cntr=0.3,0.1

Type RM Length L Ch R = 1,21669,476,476,476
BEGIN DESCRIPTION:
Bee Caves Creek 47.0
END DESCRIPTION:
XS GIS Cut Line= 3
      1817575.00     13919825.00      1817575.00     13919775.00
      1817774.97     13919575.03
#Sta/Elev= 29
  4950.4 2078.25  4952.9 2078.25  4960.4 2077.90  4970.4 2076.77  4980.4 2075.09
  4990.4 2069.14  4997.9 2057.35  5003.9 2057.35  5012.4 2055.00  5012.7 2054.50
  5016.4 2054.50  5016.6 2055.00  5028.7 2055.05  5042.4 2057.00  5057.0 2058.80
  5071.1 2060.41  5085.3 2060.07  5099.4 2059.33  5127.7 2059.19  5141.8 2059.02
  5156.0 2063.59  5170.1 2068.69  5184.2 2072.32  5198.4 2075.82  5212.5 2078.62
  5226.7 2080.35  5269.1 2085.23  5279.7 2086.27  5283.2 2086.27
#Mann=4,-1,0
  4950.4     0.1       0  5012.4    0.05       0  5016.6     0.1       0
  5042.4     0.1       0
Bank Sta=5012.4,5016.6
Exp/Cntr=0.3,0.1

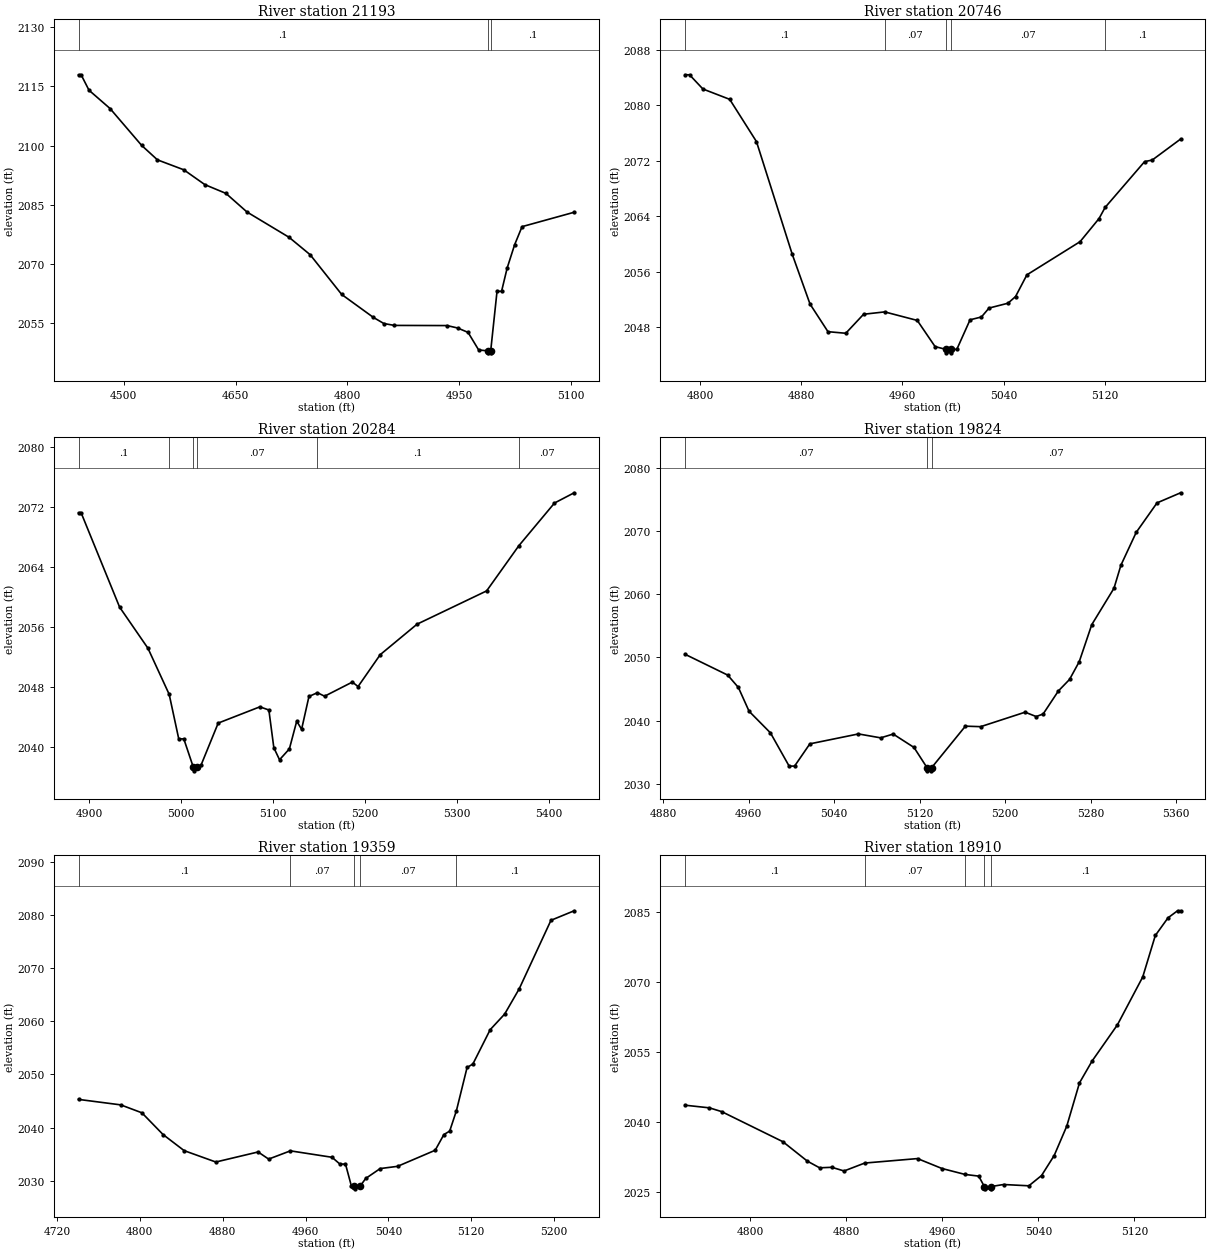
Type RM Length L Ch R = 1,21193,447,447,447
BEGIN DESCRIPTION:
Bee Caves Creek 46.0
END DESCRIPTION:
XS GIS Cut Line= 3
      1817575.01     13920374.99      1817975.00     13919975.00
      1818075.03     13919975.00
#Sta/Elev= 30
  4439.1 2117.94  4442.6 2117.94  4453.2 2114.02  4481.5 2109.38  4523.9 2100.04
  4545.1 2096.38  4580.5 2093.86  4608.8 2090.10  4637.1 2087.88  4665.4 2083.16
  4721.9 2076.75  4750.2 2072.34  4792.6 2062.26  4835.1 2056.45  4849.2 2054.90
  4863.3 2054.42  4934.1 2054.38  4948.2 2053.77  4962.3 2052.65  4976.5 2048.21
  4988.5 2047.97  4988.8 2047.47  4992.5 2047.47  4992.7 2047.97  5001.2 2063.07
  5007.3 2063.07  5014.8 2068.96  5024.8 2074.85  5034.8 2079.45  5104.8 2083.10
#Mann=3,-1,0
  4439.1     0.1       0  4988.5    0.05       0  4992.7     0.1       0
Bank Sta=4988.5,4992.7
Exp/Cntr=0.3,0.1

Type RM Length L Ch R = 1,20746,462,462,462
BEGIN DESCRIPTION:
Bee Caves Creek 45.0
END DESCRIPTION:
XS GIS Cut Line= 3
      1817974.98     13920525.02      1818125.00     13920375.00
      1818224.98     13920225.03
#Sta/Elev= 30
  4787.8 2084.37  4791.4 2084.37  4802.0 2082.32  4823.2 2080.83  4844.4 2074.74
  4872.7 2058.51  4886.8 2051.33  4901.0 2047.35  4915.1 2047.12  4929.2 2049.86
  4945.9 2050.20  4971.7 2048.97  4985.8 2045.20  4994.3 2044.80  4994.6 2044.30
  4998.3 2044.30  4998.6 2044.80  5003.0 2044.80  5013.5 2049.06  5022.5 2049.47
  5028.5 2050.75  5043.5 2051.45  5049.5 2052.41  5058.5 2055.54  5100.6 2060.32
  5115.6 2063.65  5120.4 2065.25  5151.7 2071.86  5157.7 2072.08  5180.2 2075.11
#Mann=5,-1,0
  4787.8     0.1       0  4945.9    0.07       0  4994.3    0.05       0
  4998.6    0.07       0  5120.4     0.1       0
Bank Sta=4994.3,4998.6
Exp/Cntr=0.3,0.1

Type RM Length L Ch R = 1,20284,460,460,460
BEGIN DESCRIPTION:
Bee Caves Creek 44.0
END DESCRIPTION:
XS GIS Cut Line= 3
      1818225.00     13920775.00      1818325.00     13920725.00
      1818475.00     13920325.00
#Sta/Elev= 30
  4888.4 2071.26  4891.2 2071.26  4933.1 2058.64  4963.9 2053.15  4987.0 2046.99
  4997.4 2041.04  5002.9 2041.04  5013.2 2037.27  5013.5 2036.77  5017.5 2037.27
  5021.6 2037.52  5040.3 2043.15  5085.6 2045.32  5095.4 2044.90  5100.8 2039.86
  5107.0 2038.25  5117.7 2039.70  5125.7 2043.41  5131.0 2042.32  5139.0 2046.71
  5148.2 2047.21  5156.0 2046.74  5186.2 2048.63  5192.4 2048.03  5216.5 2052.29
  5256.5 2056.36  5332.2 2060.81  5367.2 2066.84  5406.0 2072.55  5427.4 2073.92
#Mann=6,-1,0
  4888.4     0.1       0  4987.0    0.07       0  5013.2    0.05       0
  5017.5    0.07       0  5148.2     0.1       0  5367.2    0.07       0
Bank Sta=5013.2,5017.5
Exp/Cntr=0.3,0.1

Type RM Length L Ch R = 1,19824,465,465,465
BEGIN DESCRIPTION:
Bee Caves Creek 43.0
END DESCRIPTION:
XS GIS Cut Line= 3
      1818524.97     13921025.00      1818625.00     13921025.00
      1818974.97     13920925.01
#Sta/Elev= 30
  4900.3 2050.49  4940.3 2047.19  4950.3 2045.23  4960.3 2041.47  4980.3 2038.05
  4997.8 2032.79  5002.9 2032.79  5017.2 2036.31  5062.7 2037.88  5083.5 2037.26
  5095.2 2037.86  5114.7 2035.74  5126.9 2032.54  5127.2 2032.04  5130.9 2032.04
  5131.2 2032.54  5162.8 2039.11  5177.1 2039.03  5218.7 2041.32  5229.1 2040.63
  5235.6 2041.04  5249.9 2044.69  5260.3 2046.50  5269.4 2049.32  5281.1 2055.17
  5301.9 2060.93  5308.4 2064.58  5322.7 2069.77  5342.2 2074.44  5364.3 2076.04
#Mann=3,-1,0
  4900.3    0.07       0  5126.9    0.05       0  5131.2    0.07       0
Bank Sta=5126.9,5131.2
Exp/Cntr=0.3,0.1

Type RM Length L Ch R = 1,19359,449,449,449
BEGIN DESCRIPTION:
Bee Caves Creek 42.0
END DESCRIPTION:
XS GIS Cut Line= 3
      1818674.98     13921375.00      1818925.00     13921325.00
      1819125.02     13921224.99
#Sta/Elev= 30
  4740.8 2045.30  4781.6 2044.27  4802.0 2042.78  4822.4 2038.70  4842.8 2035.67
  4873.4 2033.53  4914.2 2035.42  4924.4 2034.08  4945.4 2035.63  4985.6 2034.42
  4993.2 2033.14  4998.6 2033.14  5004.2 2029.08  5006.8 2028.99  5007.3 2028.49
  5012.7 2028.99  5018.1 2030.44  5032.1 2032.30  5048.9 2032.72  5085.2 2035.74
  5093.6 2038.69  5099.2 2039.34  5105.7 2043.17  5116.0 2051.30  5121.6 2051.95
  5138.3 2058.40  5152.3 2061.34  5166.3 2066.07  5197.0 2078.96  5219.4 2080.75
#Mann=5,-1,0
  4740.8     0.1       0  4945.4    0.07       0  5006.8    0.05       0
  5012.7    0.07       0  5105.7     0.1       0
Bank Sta=5006.8,5012.7
Exp/Cntr=0.3,0.1

Type RM Length L Ch R = 1,18910,467,467,467
BEGIN DESCRIPTION:
Bee Caves Creek 41.0
END DESCRIPTION:
XS GIS Cut Line= 3
      1818724.95     13921674.99      1818975.00     13921725.00
      1819124.99     13921775.00
#Sta/Elev= 30
  4745.4 2043.62  4765.8 2043.05  4776.0 2042.24  4827.0 2035.79  4847.4 2031.62
  4857.6 2030.19  4867.8 2030.30  4878.0 2029.51  4895.2 2031.21  4939.2 2032.17
  4959.6 2030.04  4978.8 2028.77  4990.2 2028.41  4994.9 2026.18  4995.3 2025.68
  5000.3 2025.68  5000.8 2026.18  5010.9 2026.61  5032.0 2026.33  5042.6 2028.54
  5053.1 2032.82  5063.6 2039.13  5074.2 2048.41  5084.7 2053.09  5105.8 2060.85
  5126.9 2071.12  5137.4 2080.02  5148.0 2083.81  5155.9 2085.32  5158.5 2085.32
#Mann=5,-1,0
  4745.4     0.1       0  4895.2    0.07       0  4978.8     0.1       0
  4994.9    0.05       0  5000.8     0.1       0
Bank Sta=4994.9,5000.8
Exp/Cntr=0.3,0.1

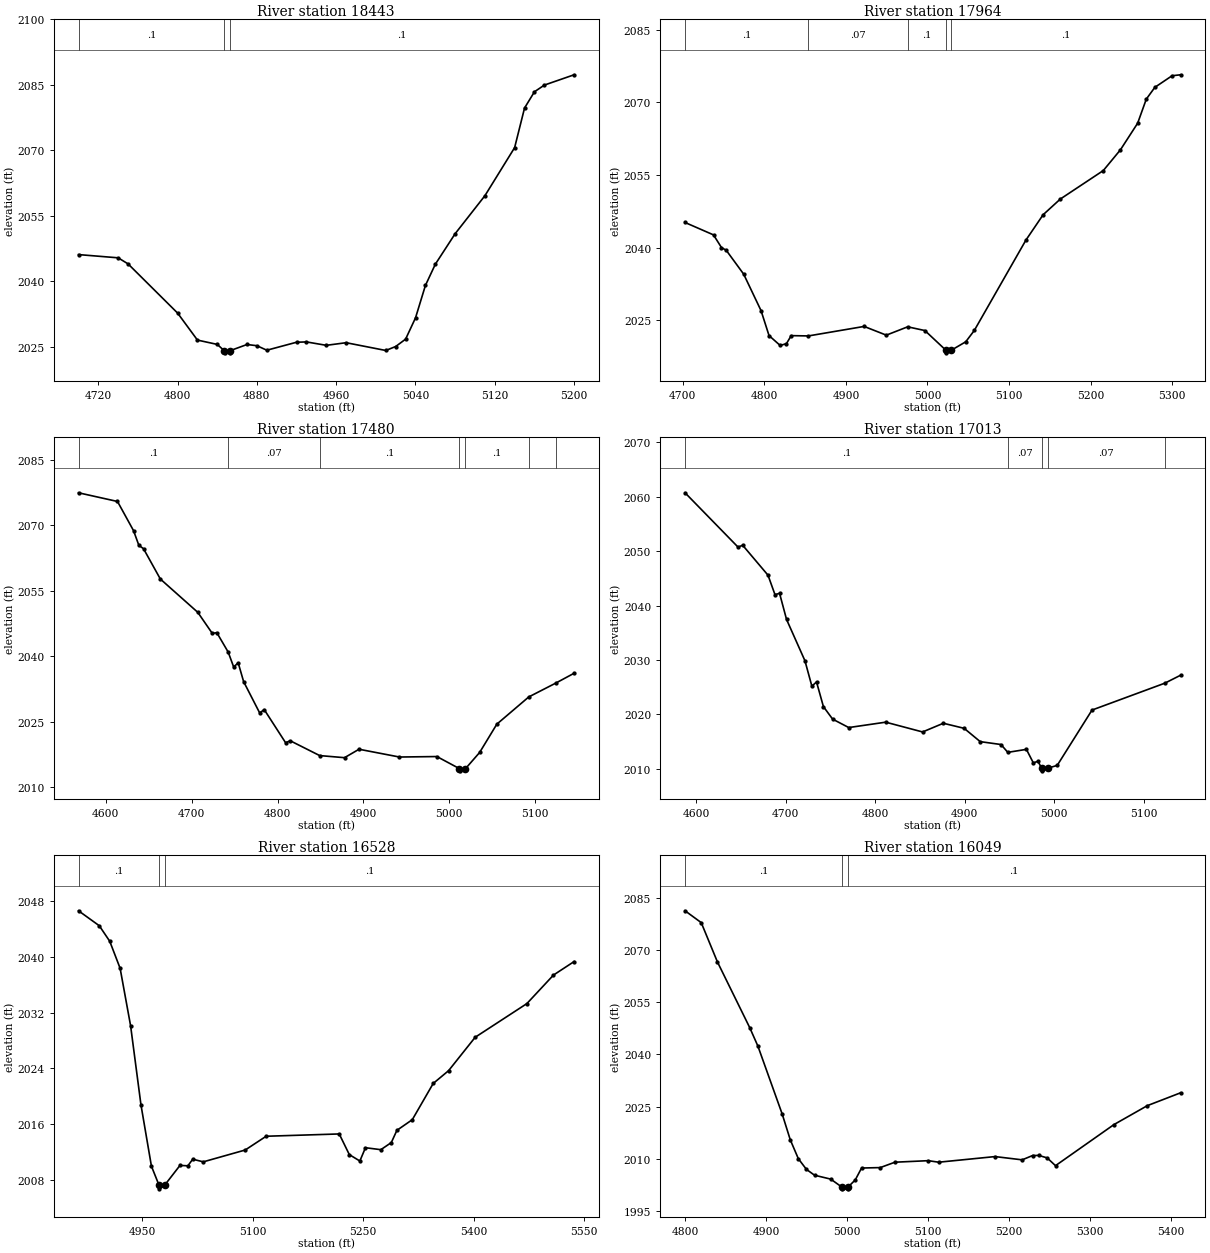
Type RM Length L Ch R = 1,18443,479,479,479
BEGIN DESCRIPTION:
Bee Caves Creek 40.0
END DESCRIPTION:
XS GIS Cut Line= 3
      1818625.02     13922175.00      1818925.00     13922175.00
      1819125.02     13922175.00
#Sta/Elev= 30
  4700.1 2046.12  4740.1 2045.38  4750.1 2043.99  4800.1 2032.72  4820.1 2026.54
  4840.1 2025.55  4847.1 2024.12  4847.6 2023.62  4852.6 2023.62  4853.1 2024.12
  4870.1 2025.53  4880.1 2025.25  4890.1 2024.22  4920.1 2026.05  4930.1 2026.12
  4950.1 2025.34  4970.1 2025.94  5010.1 2024.16  5020.1 2025.07  5030.1 2026.76
  5040.1 2031.63  5050.1 2039.06  5060.1 2043.92  5080.1 2050.91  5110.1 2059.60
  5140.1 2070.62  5150.1 2079.69  5160.1 2083.41  5170.1 2084.94  5200.1 2087.30
#Mann=3,-1,0
  4700.1     0.1       0  4847.1    0.05       0  4853.1     0.1       0
Bank Sta=4847.1,4853.1
Exp/Cntr=0.3,0.1

Type RM Length L Ch R = 1,17964,484,484,484
BEGIN DESCRIPTION:
Bee Caves Creek 39.0
END DESCRIPTION:
XS GIS Cut Line= 3
      1818575.04     13922475.02      1818825.00     13922625.00
      1819124.97     13922525.01
#Sta/Elev= 30
  4702.7 2045.21  4737.6 2042.65  4747.4 2040.03  4753.2 2039.48  4774.6 2034.55
  4795.9 2027.02  4805.7 2021.87  4819.3 2019.84  4827.0 2020.20  4832.9 2021.86
  4854.0 2021.80  4922.3 2023.76  4949.5 2021.96  4975.7 2023.68  4996.8 2022.91
  5022.8 2018.81  5023.3 2018.31  5028.8 2018.81  5046.9 2020.59  5057.4 2022.93
  5120.7 2041.58  5141.8 2046.81  5162.9 2050.05  5215.6 2055.93  5236.6 2060.21
  5257.7 2065.70  5268.3 2070.67  5278.8 2073.10  5299.9 2075.49  5310.4 2075.69
#Mann=5,-1,0
  4702.7     0.1       0  4854.0    0.07       0  4975.7     0.1       0
  5022.8    0.05       0  5028.8     0.1       0
Bank Sta=5022.8,5028.8
Exp/Cntr=0.3,0.1

Type RM Length L Ch R = 1,17480,467,467,467
BEGIN DESCRIPTION:
Bee Caves Creek 38.0
END DESCRIPTION:
XS GIS Cut Line= 3
      1818324.97     13923225.01      1818725.00     13923075.00
      1818874.97     13923075.00
#Sta/Elev= 30
  4568.2 2077.41  4613.6 2075.42  4632.3 2068.74  4638.5 2065.38  4643.9 2064.62
  4663.5 2057.68  4707.1 2050.06  4724.0 2045.24  4729.3 2045.40  4742.5 2040.97
  4748.9 2037.56  4754.2 2038.49  4760.5 2034.20  4779.2 2027.04  4784.5 2027.80
  4809.4 2020.22  4814.8 2020.67  4849.1 2017.28  4878.0 2016.80  4894.9 2018.73
  4942.0 2016.95  4985.6 2017.06  5011.9 2014.29  5012.4 2013.79  5018.9 2014.29
  5035.4 2018.00  5055.4 2024.47  5092.6 2030.70  5124.1 2033.87  5145.4 2036.12
#Mann=7,-1,0
  4568.2     0.1       0  4742.5    0.07       0  4849.1     0.1       0
  5011.9    0.05       0  5018.9     0.1       0  5092.6    0.07       0
  5124.1     0.1       0
Bank Sta=5011.9,5018.9
Exp/Cntr=0.3,0.1

Type RM Length L Ch R = 1,17013,485,485,485
BEGIN DESCRIPTION:
Bee Caves Creek 37.0
END DESCRIPTION:
XS GIS Cut Line= 3
      1818375.02     13923425.01      1818775.00     13923525.00
      1818874.99     13923425.01
#Sta/Elev= 30
  4587.7 2060.74  4646.9 2050.75  4652.1 2051.09  4680.4 2045.58  4688.2 2042.00
  4693.3 2042.25  4701.1 2037.45  4721.7 2029.83  4729.4 2025.17  4734.6 2025.95
  4742.3 2021.41  4752.6 2019.11  4770.6 2017.56  4811.9 2018.55  4853.1 2016.75
  4876.3 2018.35  4899.5 2017.42  4917.5 2014.97  4940.7 2014.44  4948.3 2013.00
  4969.1 2013.55  4976.8 2011.07  4982.0 2011.36  4986.1 2010.10  4986.6 2009.60
  4993.2 2010.10  5003.5 2010.60  5042.4 2020.78  5123.7 2025.72  5141.4 2027.19
#Mann=5,-1,0
  4587.7     0.1       0  4948.3    0.07       0  4986.1    0.05       0
  4993.2    0.07       0  5123.7     0.1       0
Bank Sta=4986.1,4993.2
Exp/Cntr=0.3,0.1

Type RM Length L Ch R = 1,16528,479,479,479
BEGIN DESCRIPTION:
Bee Caves Creek 36.0
END DESCRIPTION:
XS GIS Cut Line= 3
      1818775.03     13924074.97      1818875.00     13923975.00
      1819225.01     13923574.99
#Sta/Elev= 30
  4863.7 2046.65  4891.9 2044.50  4906.1 2042.27  4920.2 2038.38  4934.4 2030.14
  4948.5 2018.75  4962.7 2009.94  4973.1 2007.18  4973.6 2006.68  4980.5 2007.18
  5001.5 2010.05  5012.2 2009.99  5018.8 2010.94  5033.1 2010.56  5090.0 2012.26
  5118.5 2014.24  5217.7 2014.57  5231.4 2011.60  5245.7 2010.68  5253.3 2012.59
  5274.2 2012.31  5288.4 2013.33  5296.0 2015.09  5316.9 2016.62  5345.3 2021.83
  5366.2 2023.67  5402.3 2028.47  5472.5 2033.31  5508.6 2037.41  5536.6 2039.35
#Mann=3,-1,0
  4863.7     0.1       0  4973.1    0.05       0  4980.5     0.1       0
Bank Sta=4973.1,4980.5
Exp/Cntr=0.3,0.1

Type RM Length L Ch R = 1,16049,450,450,450
BEGIN DESCRIPTION:
Bee Caves Creek 35.0
END DESCRIPTION:
XS GIS Cut Line= 3
      1819275.00     13924325.02      1819275.00     13924125.00
      1819374.99     13923725.03
#Sta/Elev= 30
  4800.0 2081.38  4820.0 2077.97  4840.0 2066.66  4880.0 2047.69  4890.0 2042.42
  4920.0 2022.87  4930.0 2015.44  4940.0 2009.98  4950.0 2006.91  4960.0 2005.23
  4980.0 2004.11  4993.8 2001.81  4994.3 2001.31  5000.8 2001.31  5001.3 2001.81
  5010.3 2003.87  5018.1 2007.30  5041.2 2007.43  5059.3 2008.98  5100.5 2009.42
  5113.4 2008.98  5183.0 2010.60  5216.5 2009.66  5229.4 2010.90  5237.1 2010.93
  5247.4 2010.22  5257.7 2007.98  5329.9 2019.81  5371.1 2025.26  5412.3 2028.97
#Mann=3,-1,0
  4800.0     0.1       0  4993.8    0.05       0  5001.3     0.1       0
Bank Sta=4993.8,5001.3
Exp/Cntr=0.3,0.1