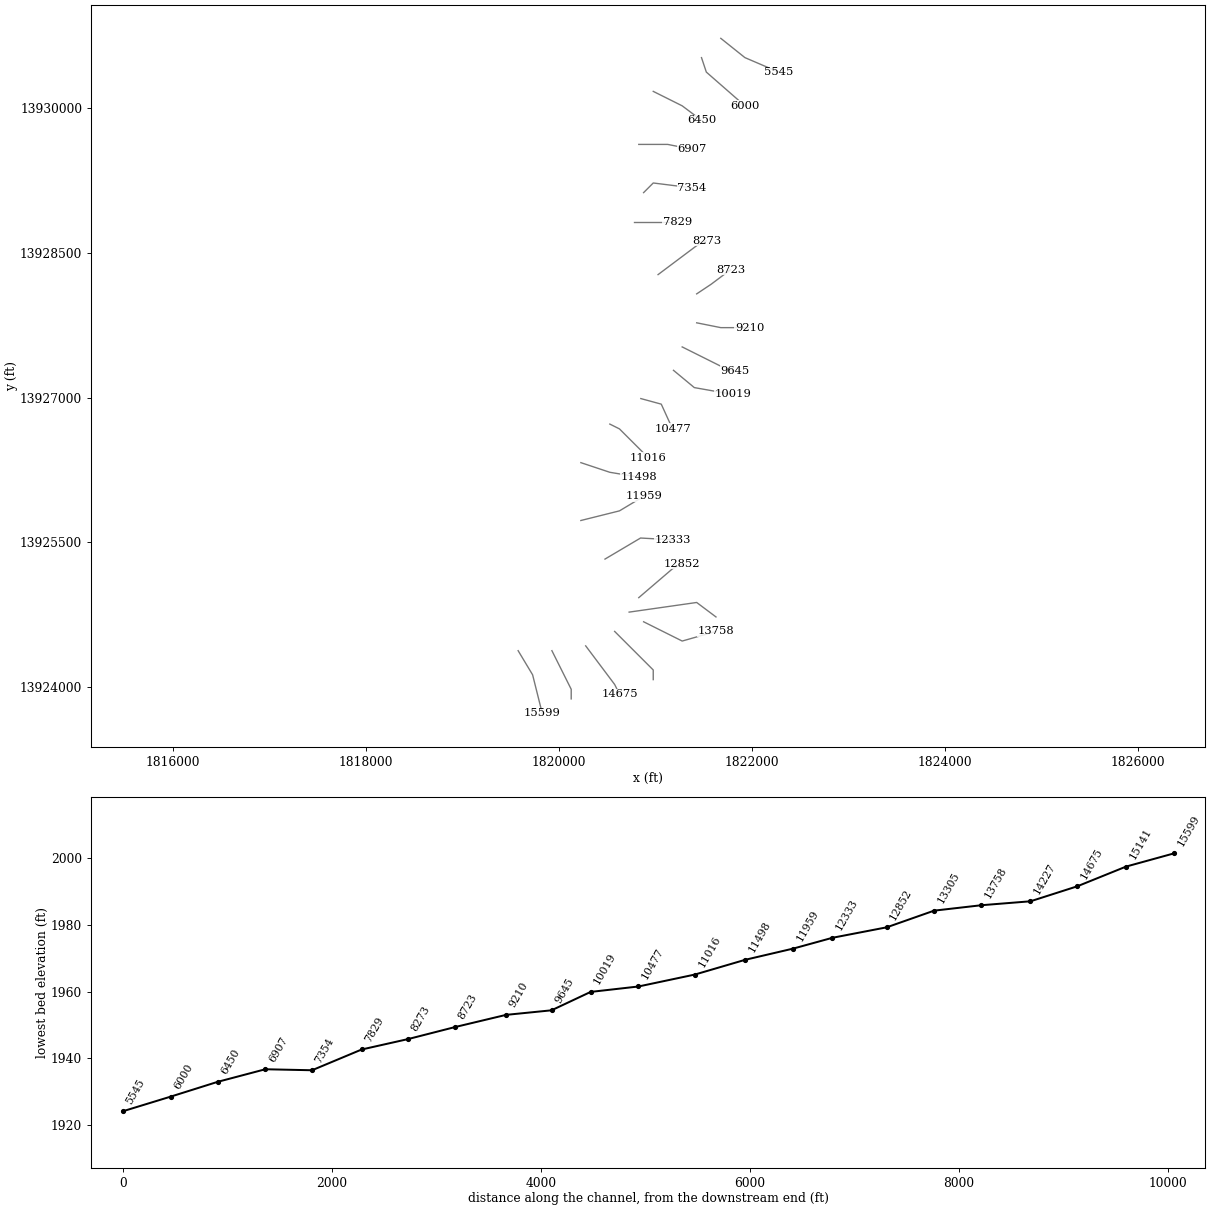
HEC-RAS study Bee Caves Creek.prj: Bee Caves Creek Base Level Engineering

--- Bee Caves Creek.g01 (geometry) --- (continued)

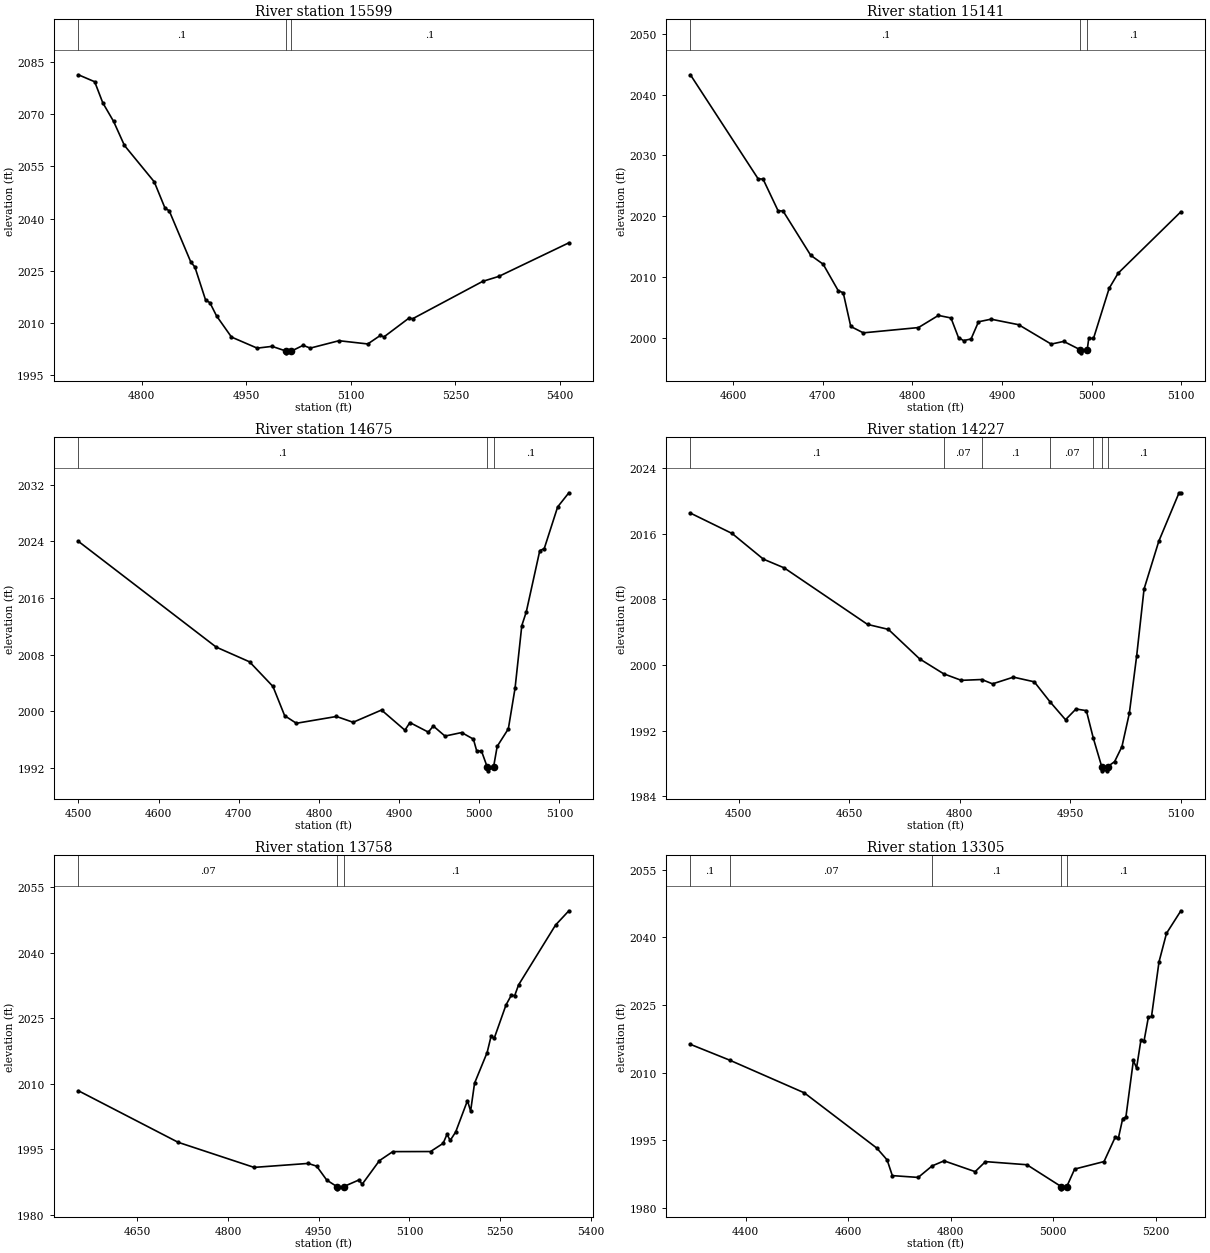
Type RM Length L Ch R = 1,15599,458,458,458
BEGIN DESCRIPTION:
Bee Caves Creek 34.0
END DESCRIPTION:
XS GIS Cut Line= 3
      1819574.98     13924375.03      1819725.00     13924125.00
      1819825.00     13923725.00
#Sta/Elev= 30
  4708.9 2081.29  4732.3 2079.29  4743.9 2073.25  4759.5 2067.88  4775.0 2061.00
  4817.8 2050.55  4833.3 2042.96  4839.2 2042.27  4870.3 2027.50  4876.1 2026.10
  4891.6 2016.52  4897.5 2015.90  4907.2 2012.05  4928.6 2005.98  4965.5 2002.80
  4986.9 2003.31  5007.0 2001.95  5007.5 2001.45  5014.6 2001.95  5031.4 2003.60
  5041.7 2002.81  5082.9 2004.93  5124.2 2004.00  5142.2 2006.44  5147.4 2006.02
  5183.5 2011.45  5188.6 2011.24  5289.1 2021.97  5312.3 2023.40  5412.8 2033.04
#Mann=3,-1,0
  4708.9     0.1       0  5007.0    0.05       0  5014.6     0.1       0
Bank Sta=5007,5014.6
Exp/Cntr=0.3,0.1

Type RM Length L Ch R = 1,15141,466,466,466
BEGIN DESCRIPTION:
Bee Caves Creek 33.0
END DESCRIPTION:
XS GIS Cut Line= 3
      1819925.00     13924375.00      1820125.00     13923975.00
      1820125.00     13923875.02
#Sta/Elev= 30
  4552.4 2043.26  4627.9 2026.15  4633.5 2026.08  4650.2 2020.88  4655.8 2020.83
  4686.6 2013.55  4700.5 2012.08  4717.3 2007.73  4722.9 2007.38  4731.3 2001.83
  4745.3 2000.78  4806.8 2001.65  4829.1 2003.65  4843.1 2003.23  4851.5 1999.99
  4857.1 1999.51  4865.5 1999.77  4873.8 2002.60  4887.8 2003.03  4918.6 2002.12
  4954.9 1998.93  4968.9 1999.37  4987.4 1997.99  4987.9 1997.49  4995.1 1997.99
  4996.8 1999.86  5002.1 1999.86  5019.6 2008.12  5029.6 2010.60  5099.6 2020.71
#Mann=3,-1,0
  4552.4     0.1       0  4987.4    0.05       0  4995.1     0.1       0
Bank Sta=4987.4,4995.1
Exp/Cntr=0.3,0.1

Type RM Length L Ch R = 1,14675,448,448,448
BEGIN DESCRIPTION:
Bee Caves Creek 32.0
END DESCRIPTION:
XS GIS Cut Line= 3
      1820275.00     13924425.00      1820575.00     13924025.00
      1820625.00     13923925.01
#Sta/Elev= 30
  4499.9 2024.00  4671.8 2009.06  4713.4 2006.98  4742.6 2003.50  4757.2 1999.37
  4771.8 1998.30  4821.8 1999.26  4842.6 1998.44  4878.0 2000.17  4907.2 1997.32
  4913.4 1998.40  4936.4 1997.05  4942.6 1997.91  4957.2 1996.49  4978.0 1996.99
  4992.6 1996.06  4996.8 1994.38  5002.7 1994.38  5010.0 1992.08  5010.5 1991.58
  5017.7 1992.08  5022.3 1995.04  5036.2 1997.51  5044.6 2003.27  5053.0 2012.10
  5058.6 2014.04  5075.4 2022.68  5081.0 2022.98  5097.7 2028.86  5111.7 2030.86
#Mann=3,-1,0
  4499.9     0.1       0  5010.0    0.05       0  5017.7     0.1       0
Bank Sta=5010,5017.7
Exp/Cntr=0.3,0.1

Type RM Length L Ch R = 1,14227,469,469,469
BEGIN DESCRIPTION:
Bee Caves Creek 31.0
END DESCRIPTION:
XS GIS Cut Line= 3
      1820575.00     13924575.00      1820975.00     13924175.00
      1820975.00     13924074.99
#Sta/Elev= 30
  4434.4 2018.55  4491.0 2016.06  4533.4 2012.93  4561.7 2011.86  4674.8 2004.96
  4703.1 2004.35  4745.5 2000.75  4778.1 1998.93  4802.1 1998.13  4829.9 1998.23
  4844.5 1997.70  4872.8 1998.52  4901.1 1997.95  4922.2 1995.54  4943.5 1993.32
  4957.7 1994.63  4971.8 1994.43  4981.2 1991.08  4992.7 1987.58  4993.2 1987.08
  5000.0 1987.08  5000.5 1987.58  5010.1 1988.20  5020.1 1990.04  5030.1 1994.09
  5040.1 2001.13  5050.1 2009.28  5070.1 2015.11  5097.6 2021.03  5100.1 2021.03
#Mann=7,-1,0
  4434.4     0.1       0  4778.1    0.07       0  4829.9     0.1       0
  4922.2    0.07       0  4981.2     0.1       0  4992.7    0.05       0
  5000.5     0.1       0
Bank Sta=4992.7,5000.5
Exp/Cntr=0.3,0.1

Type RM Length L Ch R = 1,13758,453,453,453
BEGIN DESCRIPTION:
Bee Caves Creek 30.0
END DESCRIPTION:
XS GIS Cut Line= 3
      1820875.04     13924674.98      1821275.00     13924475.00
      1821625.02     13924575.01
#Sta/Elev= 30
  4552.5 2008.36  4717.4 1996.56  4843.1 1990.81  4932.6 1991.72  4946.6 1991.09
  4963.3 1987.90  4980.2 1986.40  4980.7 1985.90  4991.1 1986.40  5016.6 1987.94
  5021.8 1986.94  5050.4 1992.36  5072.5 1994.42  5134.9 1994.44  5155.7 1996.31
  5162.2 1998.39  5167.4 1996.97  5176.5 1998.92  5196.0 2006.10  5201.2 2003.69
  5207.7 2010.08  5228.5 2017.10  5235.0 2020.81  5240.2 2020.36  5259.7 2027.99
  5268.8 2030.30  5274.0 2030.10  5280.5 2032.59  5341.6 2046.28  5363.7 2049.56
#Mann=3,-1,0
  4552.5    0.07       0  4980.2    0.05       0  4991.1     0.1       0
Bank Sta=4980.2,4991.1
Exp/Cntr=0.3,0.1

Type RM Length L Ch R = 1,13305,453,453,453
BEGIN DESCRIPTION:
Bee Caves Creek 29.0
END DESCRIPTION:
XS GIS Cut Line= 3
      1820725.00     13924775.00      1821425.00     13924875.00
      1821625.00     13924725.00
#Sta/Elev= 30
  4292.3 2016.28  4368.7 2012.79  4514.5 2005.54  4656.0 1993.30  4676.2 1990.67
  4686.3 1987.20  4736.8 1986.80  4764.0 1989.35  4787.3 1990.47  4847.9 1988.08
  4868.1 1990.30  4948.9 1989.61  5015.8 1984.77  5016.3 1984.27  5026.7 1984.77
  5042.1 1988.65  5099.4 1990.31  5121.3 1995.72  5127.5 1995.54  5135.9 1999.84
  5142.1 2000.18  5156.7 2012.71  5162.9 2011.04  5171.3 2017.16  5177.5 2017.03
  5185.9 2022.26  5192.1 2022.47  5206.7 2034.55  5221.3 2040.87  5249.4 2045.87
#Mann=5,-1,0
  4292.3     0.1       0  4368.7    0.07       0  4764.0     0.1       0
  5015.8    0.05       0  5026.7     0.1       0
Bank Sta=5015.8,5026.7
Exp/Cntr=0.3,0.1

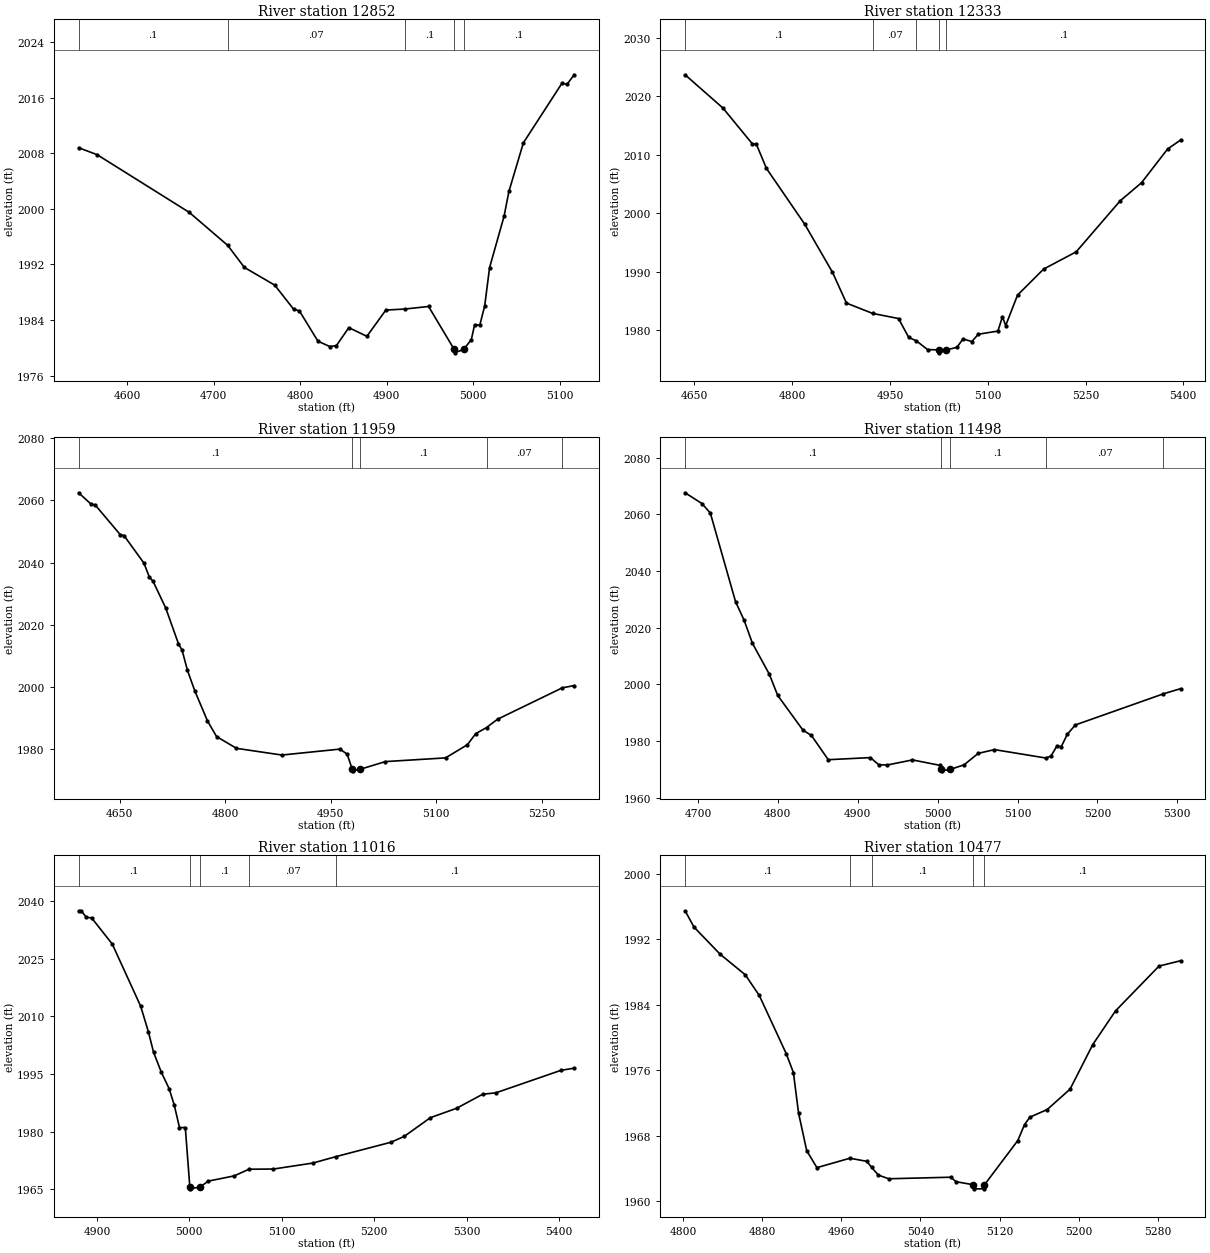
Type RM Length L Ch R = 1,12852,519,519,519
BEGIN DESCRIPTION:
Bee Caves Creek 28.0
END DESCRIPTION:
XS GIS Cut Line= 3
      1820824.97     13924924.97      1821175.00     13925225.00
      1821274.98     13925274.99
#Sta/Elev= 30
  4544.0 2008.81  4565.4 2007.81  4671.9 1999.50  4716.3 1994.75  4735.6 1991.57
  4770.7 1989.02  4792.6 1985.54  4799.2 1985.31  4820.6 1980.95  4834.3 1980.18
  4842.0 1980.32  4856.3 1982.90  4877.2 1981.65  4899.1 1985.43  4921.3 1985.58
  4948.5 1985.95  4978.1 1979.77  4978.6 1979.27  4989.1 1979.77  4997.9 1981.17
  5001.7 1983.30  5007.8 1983.30  5013.4 1986.05  5019.0 1991.54  5035.8 1998.96
  5041.4 2002.54  5058.1 2009.52  5102.8 2018.12  5108.4 2017.93  5116.8 2019.32
#Mann=5,-1,0
  4544.0     0.1       0  4716.3    0.07       0  4921.3     0.1       0
  4978.1    0.05       0  4989.1     0.1       0
Bank Sta=4978.1,4989.1
Exp/Cntr=0.3,0.1

Type RM Length L Ch R = 1,12333,374,374,374
BEGIN DESCRIPTION:
Bee Caves Creek 27.0
END DESCRIPTION:
XS GIS Cut Line= 3
      1820475.00     13925325.00      1820843.44     13925543.34
      1821174.95     13925525.00
#Sta/Elev= 30
  4635.6 2023.66  4693.7 2017.97  4738.9 2011.83  4744.8 2011.83  4760.4 2007.66
  4818.9 1998.16  4861.7 1989.91  4883.2 1984.63  4923.3 1982.87  4963.1 1981.99
  4978.7 1978.76  4990.3 1978.19  5007.6 1976.69  5025.2 1976.63  5025.7 1976.13
  5036.4 1976.63  5052.8 1977.08  5061.9 1978.51  5075.5 1978.06  5085.5 1979.31
  5115.5 1979.85  5122.5 1982.30  5127.5 1980.79  5145.6 1985.99  5185.6 1990.44
  5235.7 1993.40  5303.1 2002.11  5335.9 2005.21  5375.9 2010.97  5395.9 2012.51
#Mann=5,-1,0
  4635.6     0.1       0  4923.3    0.07       0  4990.3     0.1       0
  5025.2    0.05       0  5036.4     0.1       0
Bank Sta=5025.2,5036.4
Exp/Cntr=0.3,0.1

Type RM Length L Ch R = 1,11959,461,461,461
BEGIN DESCRIPTION:
Bee Caves Creek 26.0
END DESCRIPTION:
XS GIS Cut Line= 3
      1820224.98     13925724.99      1820625.00     13925825.00
      1820875.02     13925975.01
#Sta/Elev= 30
  4591.9 2062.48  4610.0 2058.72  4615.1 2058.64  4651.2 2048.94  4656.3 2048.70
  4684.7 2039.81  4692.4 2035.29  4697.6 2033.98  4715.6 2025.36  4733.7 2013.84
  4738.8 2011.81  4746.5 2005.27  4756.8 1998.72  4774.9 1988.99  4787.8 1983.95
  4816.1 1980.15  4880.5 1977.99  4963.0 1979.90  4973.3 1978.28  4980.6 1973.40
  4981.1 1972.90  4991.8 1973.40  5027.6 1975.88  5113.1 1977.07  5144.2 1981.33
  5155.8 1984.85  5171.3 1986.84  5186.9 1989.52  5278.9 1999.64  5295.8 2000.37
#Mann=5,-1,0
  4591.9     0.1       0  4980.6    0.05       0  4991.8     0.1       0
  5171.3    0.07       0  5278.9     0.1       0
Bank Sta=4980.6,4991.8
Exp/Cntr=0.3,0.1

Type RM Length L Ch R = 1,11498,482,482,482
BEGIN DESCRIPTION:
Bee Caves Creek 25.0
END DESCRIPTION:
XS GIS Cut Line= 3
      1820225.02     13926324.99      1820525.00     13926225.00
      1820824.96     13926175.01
#Sta/Elev= 30
  4683.9 2067.63  4705.0 2063.83  4715.5 2060.47  4747.1 2029.16  4757.7 2022.70
  4768.2 2014.52  4789.3 2003.63  4799.8 1996.14  4831.4 1983.88  4842.0 1982.02
  4863.1 1973.45  4915.8 1974.19  4926.3 1971.68  4936.9 1971.58  4968.5 1973.37
  5002.6 1971.48  5004.6 1970.02  5005.1 1969.52  5015.8 1970.02  5033.1 1971.64
  5050.8 1975.68  5071.1 1977.01  5135.5 1974.04  5142.0 1974.77  5149.6 1978.43
  5154.7 1977.99  5162.3 1982.41  5172.4 1985.71  5282.6 1996.69  5304.2 1998.52
#Mann=5,-1,0
  4683.9     0.1       0  5004.6    0.05       0  5015.8     0.1       0
  5135.5    0.07       0  5282.6     0.1       0
Bank Sta=5004.6,5015.8
Exp/Cntr=0.3,0.1

Type RM Length L Ch R = 1,11016,539,539,539
BEGIN DESCRIPTION:
Bee Caves Creek 24.0
END DESCRIPTION:
XS GIS Cut Line= 3
      1820524.96     13926725.02      1820625.00     13926675.00
      1820924.99     13926375.01
#Sta/Elev= 30
  4880.2 2037.51  4883.0 2037.51  4888.6 2035.79  4894.2 2035.67  4916.6 2028.84
  4947.3 2012.67  4955.7 2005.97  4961.3 2000.63  4969.7 1995.43  4978.1 1991.19
  4983.7 1986.86  4989.3 1981.05  4995.6 1981.05  5000.5 1965.59  5001.0 1965.09
  5011.8 1965.59  5020.3 1967.09  5048.6 1968.47  5064.5 1970.20  5091.0 1970.25
  5133.5 1971.80  5158.7 1973.49  5218.3 1977.24  5232.5 1978.76  5260.8 1983.63
  5289.0 1986.06  5317.3 1989.73  5331.5 1990.09  5402.2 1995.97  5416.3 1996.51
#Mann=5,-1,0
  4880.2     0.1       0  5000.5    0.05       0  5011.8     0.1       0
  5064.5    0.07       0  5158.7     0.1       0
Bank Sta=5000.5,5011.8
Exp/Cntr=0.3,0.1

Type RM Length L Ch R = 1,10477,458,458,458
BEGIN DESCRIPTION:
Bee Caves Creek 23.0
END DESCRIPTION:
XS GIS Cut Line= 3
      1820846.29     13926989.43      1821058.15     13926931.57
      1821174.98     13926675.04
#Sta/Elev= 30
  4801.8 1995.48  4810.8 1993.49  4837.2 1990.18  4862.7 1987.66  4876.9 1985.13
  4904.1 1978.04  4911.4 1975.72  4916.6 1970.78  4924.9 1966.16  4935.2 1964.10
  4968.6 1965.25  4985.7 1964.87  4990.6 1964.13  4997.4 1963.19  5007.8 1962.74
  5070.6 1962.93  5076.1 1962.38  5093.5 1962.01  5094.0 1961.51  5104.3 1961.51
  5104.8 1962.01  5138.5 1967.41  5145.3 1969.36  5150.8 1970.27  5168.3 1971.20
  5191.4 1973.69  5214.4 1979.14  5237.4 1983.25  5281.4 1988.72  5303.3 1989.38
#Mann=5,-1,0
  4801.8     0.1       0  4968.6    0.07       0  4990.6     0.1       0
  5093.5    0.05       0  5104.8     0.1       0
Bank Sta=5093.5,5104.8
Exp/Cntr=0.3,0.1

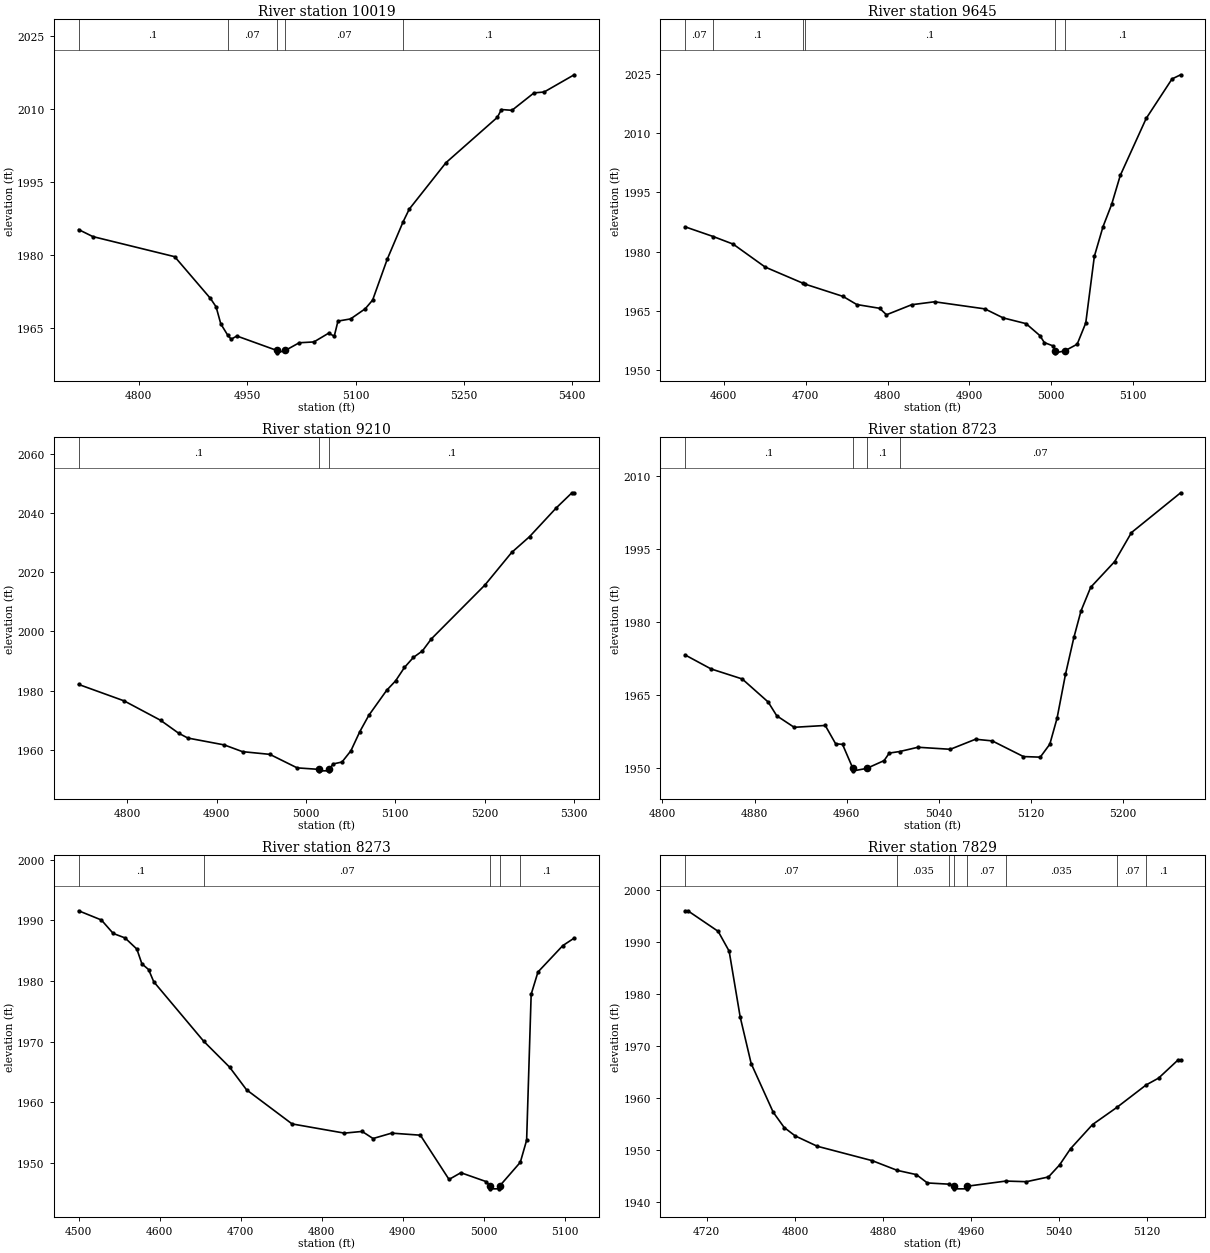
Type RM Length L Ch R = 1,10019,374,374,374
BEGIN DESCRIPTION:
Bee Caves Creek 22.0
END DESCRIPTION:
XS GIS Cut Line= 3
      1821184.65     13927282.47      1821400.57     13927103.28
      1821799.76     13927032.53
#Sta/Elev= 30
  4716.7 1985.20  4736.4 1983.76  4849.7 1979.63  4899.2 1971.05  4907.0 1969.33
  4913.5 1965.83  4923.2 1963.48  4927.9 1962.68  4935.7 1963.34  4990.9 1960.38
  4991.4 1959.88  5002.9 1960.38  5022.1 1961.95  5042.4 1962.12  5062.7 1963.91
  5070.6 1963.31  5075.7 1966.40  5093.2 1966.85  5113.5 1968.94  5123.7 1970.72
  5144.0 1979.14  5165.9 1986.80  5174.4 1989.40  5225.2 1998.94  5296.3 2008.25
  5302.0 2009.86  5316.6 2009.70  5347.1 2013.28  5361.1 2013.46  5402.7 2017.00
#Mann=5,-1,0
  4716.7     0.1       0  4923.2    0.07       0  4990.9    0.05       0
  5002.9    0.07       0  5165.9     0.1       0
Bank Sta=4990.9,5002.9
Exp/Cntr=0.3,0.1

Type RM Length L Ch R = 1,9645,435,435,435
BEGIN DESCRIPTION:
Bee Caves Creek 21.0
END DESCRIPTION:
XS GIS Cut Line= 3
      1821274.98     13927525.01      1821675.00     13927325.00
      1821824.95     13927275.02
#Sta/Elev= 30
  4552.7 1986.27  4587.2 1983.80  4611.4 1981.89  4650.5 1976.08  4696.5 1972.00
  4698.8 1971.79  4745.6 1968.65  4762.4 1966.59  4790.3 1965.64  4798.7 1964.00
  4829.4 1966.54  4857.4 1967.29  4918.9 1965.49  4941.2 1963.21  4969.2 1961.75
  4986.0 1958.74  4991.5 1956.96  5002.6 1956.08  5004.5 1954.86  5005.0 1954.36
  5016.5 1954.86  5031.6 1956.54  5042.1 1961.92  5052.6 1978.80  5063.2 1986.32
  5073.7 1991.93  5084.3 1999.30  5115.9 2013.71  5147.5 2023.72  5158.0 2024.77
#Mann=6,-1,0
  4552.7    0.07       0  4587.2     0.1       0  4696.5    0.07       0
  4698.8     0.1       0  5004.5    0.05       0  5016.5     0.1       0
Bank Sta=5004.5,5016.5
Exp/Cntr=0.3,0.1

Type RM Length L Ch R = 1,9210,487,487,487
BEGIN DESCRIPTION:
Bee Caves Creek 20.0
END DESCRIPTION:
XS GIS Cut Line= 3
      1821425.04     13927774.99      1821675.00     13927725.00
      1821974.99     13927725.00
#Sta/Elev= 30
  4745.5 1982.13  4796.4 1976.59  4837.2 1970.05  4857.6 1965.66  4867.8 1964.05
  4908.6 1961.73  4929.0 1959.46  4959.6 1958.55  4990.2 1953.99  5014.4 1953.49
  5014.9 1952.99  5025.9 1952.99  5026.4 1953.49  5030.4 1955.31  5040.4 1955.96
  5050.4 1959.76  5060.4 1966.23  5070.4 1971.69  5090.4 1980.14  5100.4 1983.33
  5110.4 1987.87  5120.4 1991.26  5130.4 1993.41  5140.4 1997.47  5200.4 2015.64
  5230.4 2026.64  5250.4 2031.96  5280.4 2041.69  5297.9 2046.77  5300.4 2046.77
#Mann=3,-1,0
  4745.5     0.1       0  5014.4    0.05       0  5026.4     0.1       0
Bank Sta=5014.4,5026.4
Exp/Cntr=0.3,0.1

Type RM Length L Ch R = 1,8723,450,450,450
BEGIN DESCRIPTION:
Bee Caves Creek 19.0
END DESCRIPTION:
XS GIS Cut Line= 3
      1821424.99     13928075.00      1821575.00     13928175.00
      1821775.01     13928325.01
#Sta/Elev= 30
  4819.7 1973.22  4842.2 1970.34  4869.3 1968.27  4891.8 1963.53  4899.3 1960.68
  4914.4 1958.31  4941.4 1958.69  4950.4 1954.92  4956.4 1954.79  4965.4 1949.84
  4965.9 1949.34  4977.4 1949.84  4992.5 1951.45  4997.0 1953.00  5006.1 1953.32
  5021.9 1954.20  5050.0 1953.78  5071.9 1955.85  5086.4 1955.51  5113.5 1952.28
  5128.1 1952.16  5136.4 1954.83  5142.7 1960.19  5150.0 1969.22  5157.3 1976.82
  5163.5 1982.30  5171.9 1987.16  5192.7 1992.45  5207.3 1998.43  5250.0 2006.63
#Mann=4,-1,0
  4819.7     0.1       0  4965.4    0.05       0  4977.4     0.1       0
  5006.1    0.07       0
Bank Sta=4965.4,4977.4
Exp/Cntr=0.3,0.1

Type RM Length L Ch R = 1,8273,444,444,444
BEGIN DESCRIPTION:
Bee Caves Creek 18.0
END DESCRIPTION:
XS GIS Cut Line= 3
      1821025.02     13928275.01      1821425.00     13928575.00
      1821525.02     13928625.01
#Sta/Elev= 30
  4499.8 1991.60  4527.9 1990.08  4542.5 1987.86  4557.1 1987.12  4571.7 1985.28
  4577.9 1982.85  4586.2 1981.90  4592.5 1979.90  4654.2 1970.08  4686.2 1965.80
  4707.1 1962.07  4763.3 1956.44  4827.9 1954.92  4849.8 1955.20  4863.3 1954.03
  4886.2 1954.92  4921.7 1954.58  4957.1 1947.28  4971.7 1948.39  5002.6 1946.94
  5007.7 1946.23  5008.2 1945.73  5019.3 1945.73  5019.8 1946.23  5045.1 1950.11
  5052.9 1953.75  5058.5 1977.82  5066.9 1981.50  5097.6 1985.86  5111.6 1987.09
#Mann=5,-1,0
  4499.8     0.1       0  4654.2    0.07       0  5007.7    0.05       0
  5019.8    0.07       0  5045.1     0.1       0
Bank Sta=5007.7,5019.8
Exp/Cntr=0.3,0.1

Type RM Length L Ch R = 1,7829,475,475,475
BEGIN DESCRIPTION:
Bee Caves Creek 17.0
END DESCRIPTION:
XS GIS Cut Line= 3
      1820775.00     13928825.00      1821075.00     13928825.00
      1821225.00     13928825.00
#Sta/Elev= 30
  4700.3 1995.93  4702.8 1995.93  4730.3 1991.99  4740.3 1988.19  4750.3 1975.59
  4760.3 1966.63  4780.3 1957.30  4790.3 1954.36  4800.3 1952.75  4820.3 1950.77
  4870.3 1948.00  4893.0 1946.14  4910.3 1945.33  4920.3 1943.73  4939.5 1943.50
  4944.3 1943.10  4944.8 1942.60  4955.9 1942.60  4956.4 1943.10  4991.5 1944.09
  5010.3 1943.97  5030.3 1944.88  5040.3 1947.17  5050.3 1950.29  5070.3 1954.93
  5092.4 1958.22  5119.0 1962.53  5130.3 1963.84  5147.8 1967.29  5150.3 1967.29
#Mann=8,-1,0
  4700.3    0.07       0  4893.0   0.035       0  4939.5    0.07       0
  4944.3   0.035       0  4956.4    0.07       0  4991.5   0.035       0
  5092.4    0.07       0  5119.0     0.1       0
Bank Sta=4944.3,4956.4
Exp/Cntr=0.3,0.1

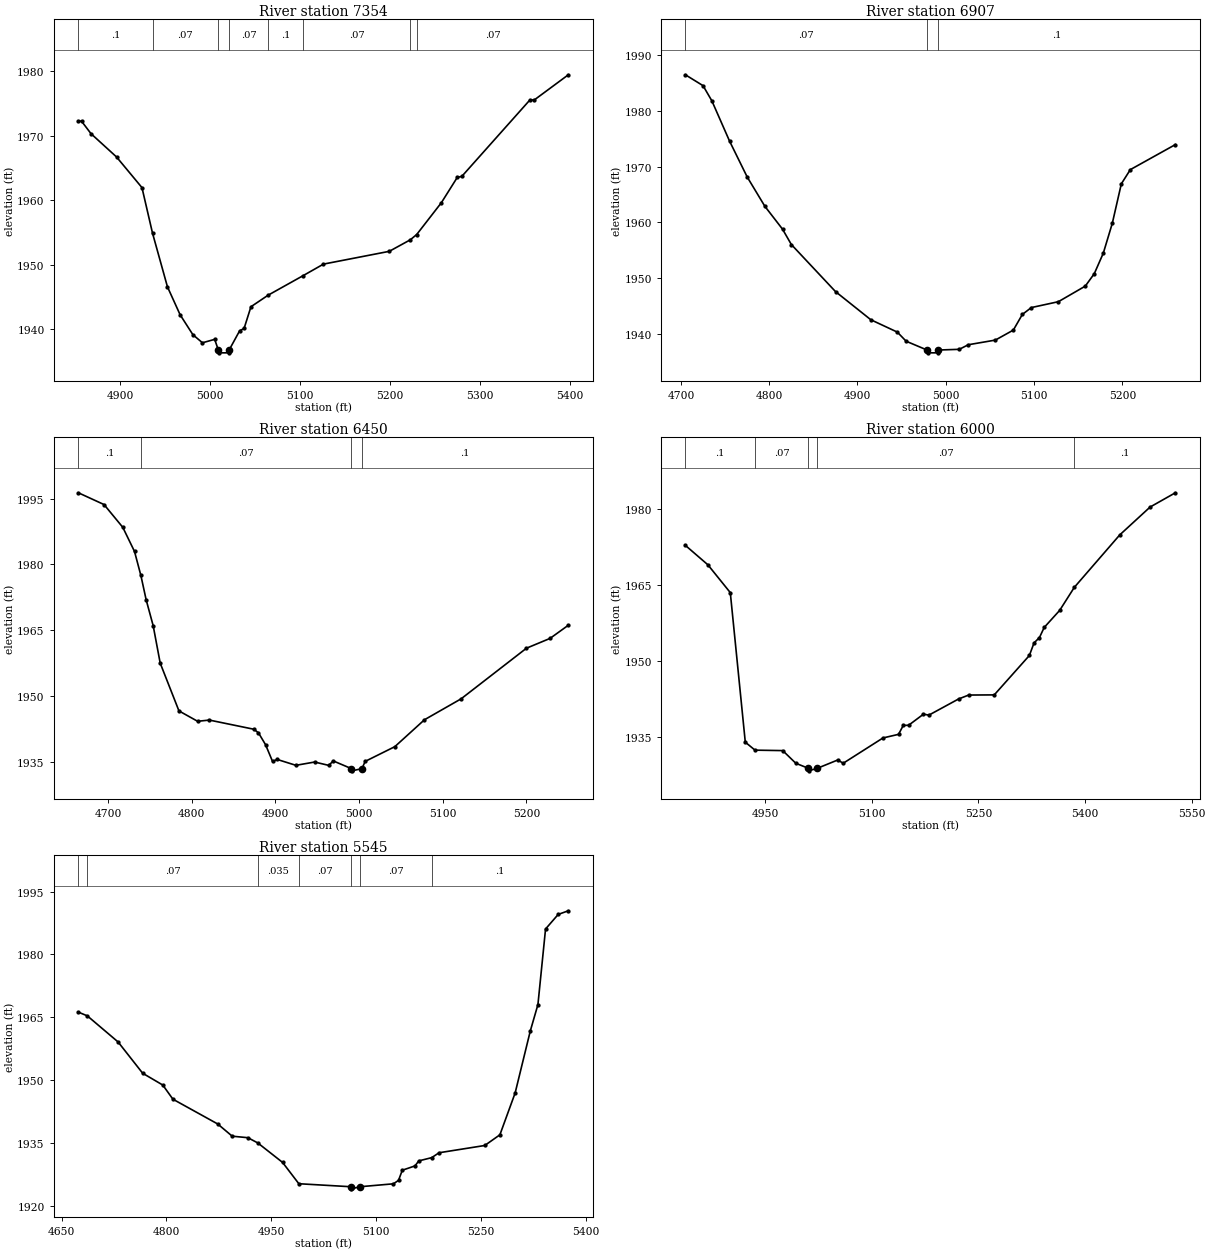
Type RM Length L Ch R = 1,7354,447,447,447
BEGIN DESCRIPTION:
Bee Caves Creek 16.0
END DESCRIPTION:
XS GIS Cut Line= 3
      1820875.00     13929125.00      1820975.00     13929225.00
      1821374.97     13929175.00
#Sta/Elev= 30
  4853.8 1972.30  4857.3 1972.30  4867.9 1970.35  4896.2 1966.75  4924.5 1961.99
  4936.2 1954.94  4952.8 1946.61  4966.9 1942.27  4981.1 1939.18  4991.7 1937.93
  5005.3 1938.46  5009.2 1936.87  5009.7 1936.37  5021.1 1936.37  5021.6 1936.87
  5033.0 1939.78  5038.0 1940.16  5045.6 1943.52  5064.8 1945.32  5103.7 1948.35
  5126.2 1950.13  5199.3 1952.11  5222.7 1953.90  5229.8 1954.72  5257.2 1959.65
  5274.9 1963.58  5279.9 1963.73  5355.5 1975.57  5360.5 1975.59  5398.3 1979.49
#Mann=8,-1,0
  4853.8     0.1       0  4936.2    0.07       0  5009.2    0.05       0
  5021.6    0.07       0  5064.8     0.1       0  5103.7    0.07       0
  5222.7     0.1       0  5229.8    0.07       0
Bank Sta=5009.2,5021.6
Exp/Cntr=0.3,0.1

Type RM Length L Ch R = 1,6907,457,457,457
BEGIN DESCRIPTION:
Bee Caves Creek 15.0
END DESCRIPTION:
XS GIS Cut Line= 3
      1820825.02     13929625.00      1821125.00     13929625.00
      1821374.97     13929575.01
#Sta/Elev= 30
  4705.1 1986.42  4725.1 1984.47  4735.1 1981.75  4755.1 1974.56  4775.1 1968.13
  4795.1 1962.89  4815.1 1958.80  4825.1 1956.05  4875.1 1947.63  4915.1 1942.59
  4945.1 1940.38  4955.1 1938.75  4978.8 1937.17  4979.3 1936.67  4990.8 1936.67
  4991.3 1937.17  5015.3 1937.30  5025.5 1938.12  5056.1 1938.95  5076.5 1940.74
  5086.7 1943.54  5096.9 1944.77  5127.5 1945.82  5158.0 1948.61  5168.2 1950.84
  5178.4 1954.51  5188.6 1959.86  5198.8 1966.91  5209.0 1969.45  5260.0 1973.93
#Mann=3,-1,0
  4705.1    0.07       0  4978.8    0.05       0  4991.3     0.1       0
Bank Sta=4978.8,4991.3
Exp/Cntr=0.3,0.1

Type RM Length L Ch R = 1,6450,450,450,450
BEGIN DESCRIPTION:
Bee Caves Creek 14.0
END DESCRIPTION:
XS GIS Cut Line= 3
      1820975.01     13930174.99      1821275.00     13930025.00
      1821475.01     13929875.00
#Sta/Elev= 30
  4664.6 1996.36  4695.3 1993.67  4717.7 1988.47  4731.7 1982.96  4739.3 1977.48
  4745.6 1971.93  4754.0 1966.01  4762.4 1957.46  4784.8 1946.56  4807.1 1944.19
  4821.1 1944.47  4874.2 1942.38  4879.8 1941.55  4888.2 1938.87  4896.6 1935.03
  4902.2 1935.48  4924.5 1934.14  4946.9 1934.89  4963.7 1934.13  4969.2 1935.14
  4990.9 1933.38  4991.4 1932.88  5003.4 1933.38  5007.3 1935.04  5042.7 1938.40
  5078.1 1944.54  5121.9 1949.32  5200.0 1960.88  5228.1 1963.11  5250.0 1966.12
#Mann=4,-1,0
  4664.6     0.1       0  4739.3    0.07       0  4990.9    0.05       0
  5003.4     0.1       0
Bank Sta=4990.9,5003.4
Exp/Cntr=0.3,0.1

Type RM Length L Ch R = 1,6000,455,455,455
BEGIN DESCRIPTION:
Bee Caves Creek 13.0
END DESCRIPTION:
XS GIS Cut Line= 3
      1821475.01     13930524.96      1821525.00     13930375.00
      1821925.02     13930024.99
#Sta/Elev= 30
  4837.5 1972.79  4869.1 1968.98  4900.7 1963.50  4921.8 1934.08  4935.5 1932.51
  4974.5 1932.42  4992.9 1929.93  5010.6 1928.94  5011.1 1928.44  5023.2 1928.94
  5052.0 1930.58  5059.6 1929.93  5115.6 1934.91  5137.5 1935.62  5144.1 1937.37
  5151.7 1937.41  5172.6 1939.59  5180.2 1939.40  5221.9 1942.57  5236.2 1943.35
  5272.2 1943.38  5321.6 1951.13  5328.2 1953.61  5335.8 1954.66  5342.5 1956.65
  5364.3 1960.01  5384.9 1964.54  5448.8 1974.85  5491.5 1980.33  5527.1 1983.14
#Mann=5,-1,0
  4837.5     0.1       0  4935.5    0.07       0  5010.6    0.05       0
  5023.2    0.07       0  5384.9     0.1       0
Bank Sta=5010.6,5023.2
Exp/Cntr=0.3,0.1

Type RM Length L Ch R = 1,5545,470,470,470
BEGIN DESCRIPTION:
Bee Caves Creek 12.0
END DESCRIPTION:
XS GIS Cut Line= 3
      1821675.01     13930724.99      1821925.00     13930525.00
      1822274.97     13930375.01
#Sta/Elev= 30
  4674.1 1966.23  4686.9 1965.34  4730.9 1959.12  4766.1 1951.65  4794.9 1948.83
  4809.4 1945.45  4873.4 1939.55  4894.2 1936.63  4916.6 1936.27  4930.7 1935.03
  4966.2 1930.38  4989.5 1925.29  5064.1 1924.57  5064.6 1924.07  5076.8 1924.57
  5124.8 1925.27  5132.1 1926.10  5137.5 1928.51  5155.6 1929.54  5161.1 1930.74
  5179.5 1931.51  5190.1 1932.68  5255.4 1934.41  5277.1 1936.96  5298.9 1946.94
  5320.6 1961.74  5331.5 1968.03  5342.4 1986.06  5360.5 1989.54  5375.0 1990.41
#Mann=7,-1,0
  4674.1     0.1       0  4686.9    0.07       0  4930.7   0.035       0
  4989.5    0.07       0  5064.1    0.05       0  5076.8    0.07       0
  5179.5     0.1       0
Bank Sta=5064.1,5076.8
Exp/Cntr=0.3,0.1