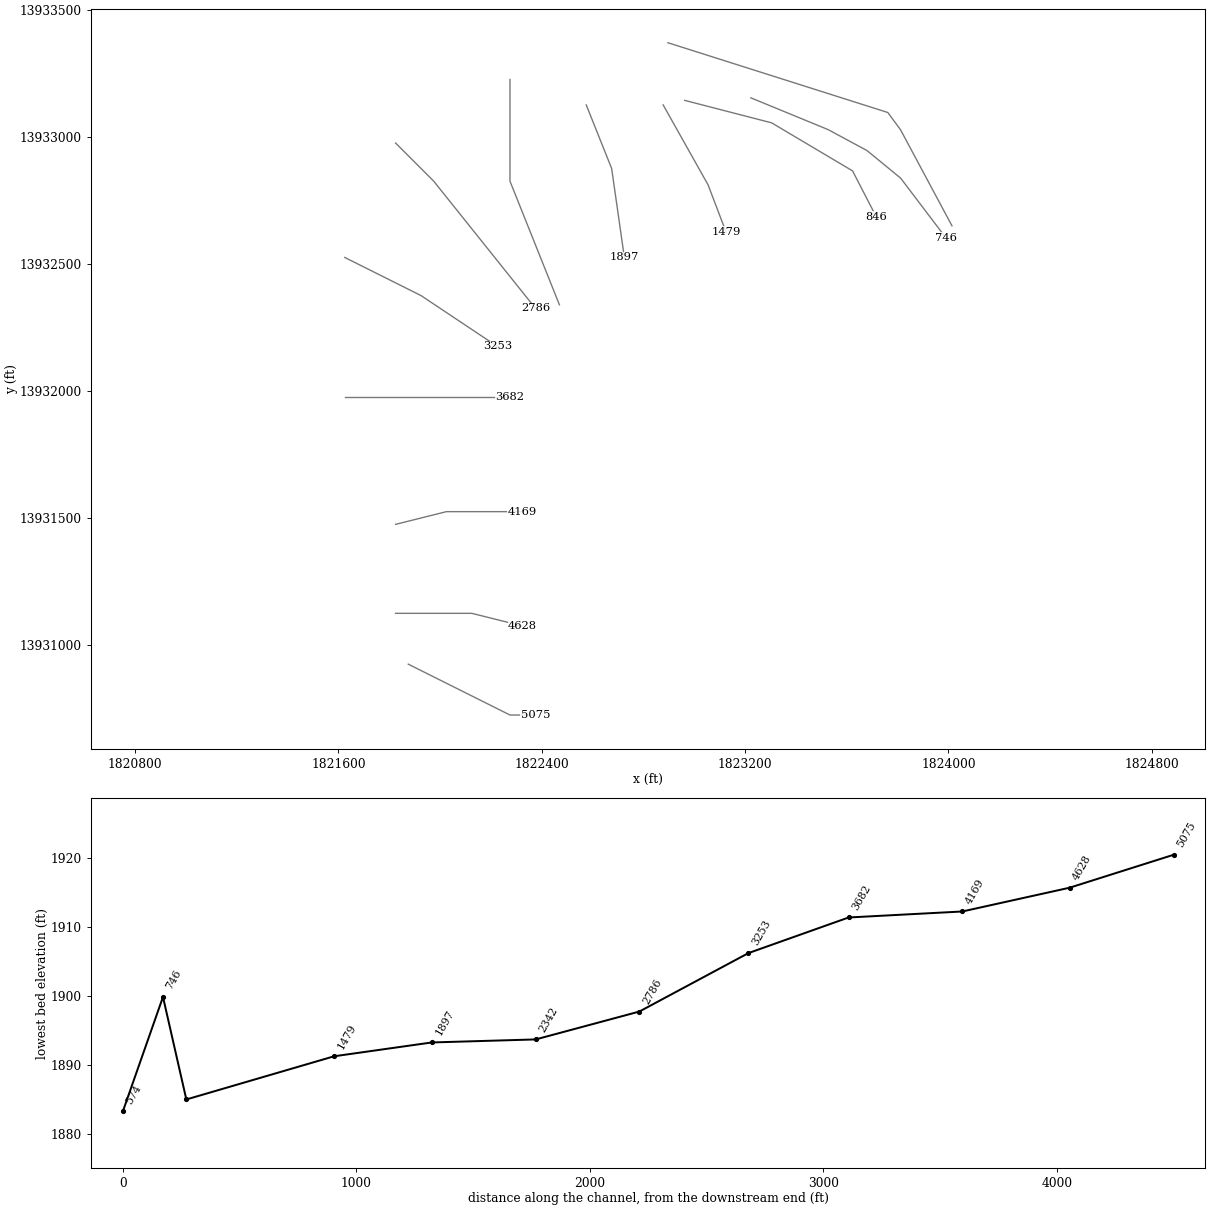
HEC-RAS study Bee Caves Creek.prj: Bee Caves Creek Base Level Engineering

--- Bee Caves Creek.g01 (geometry) --- (continued)

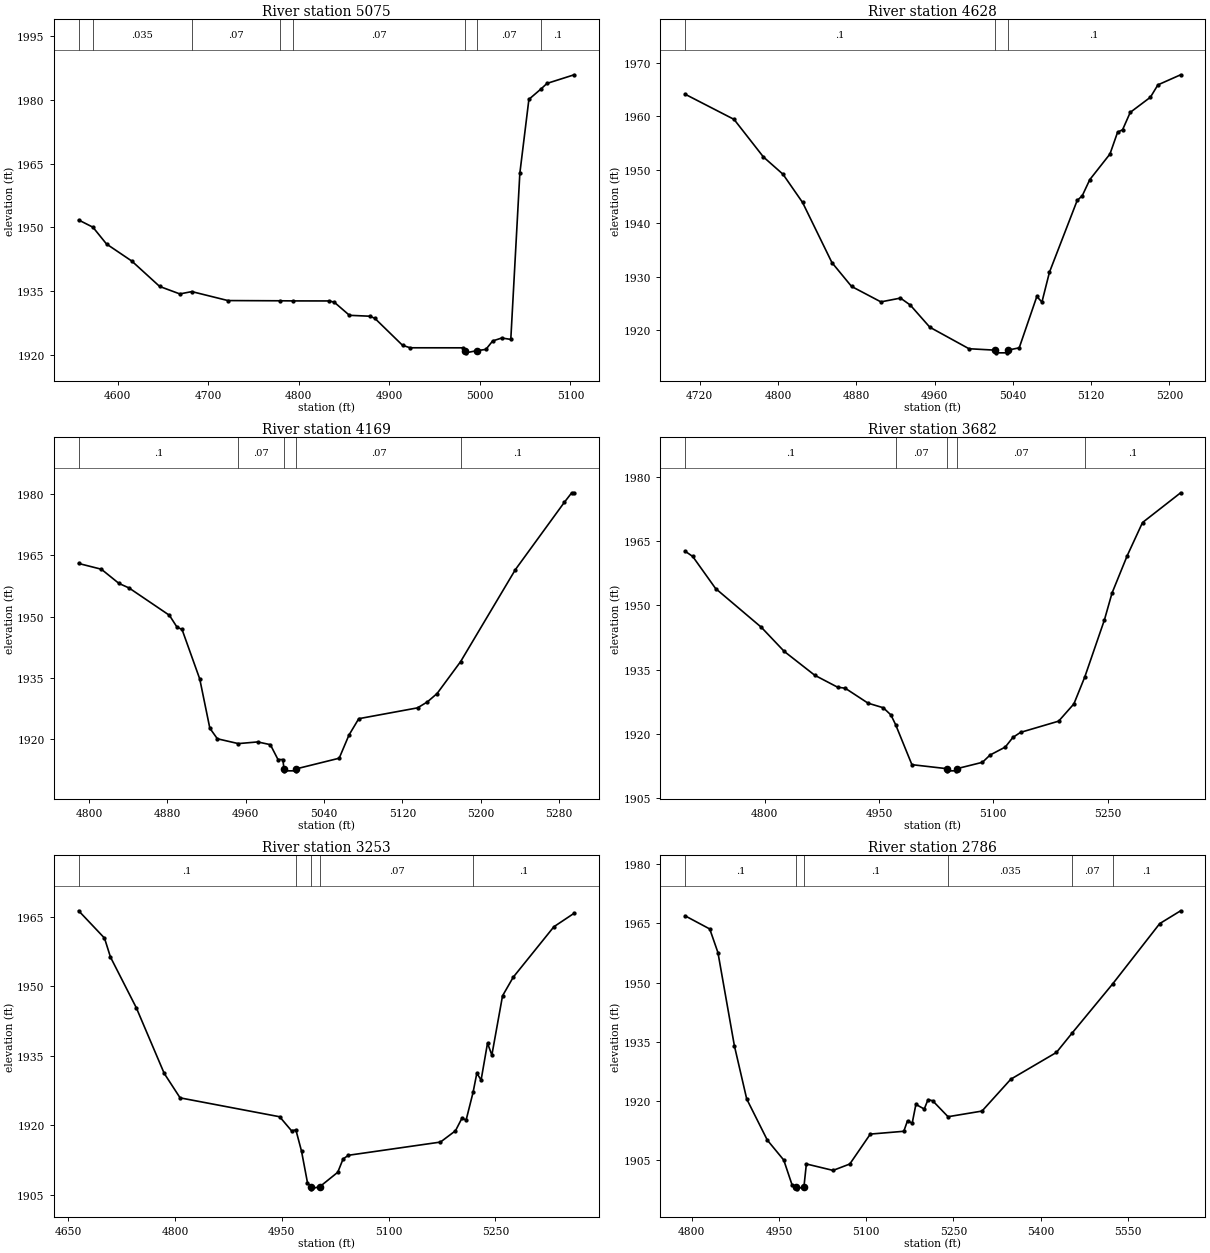
Type RM Length L Ch R = 1,5075,447,447,447
BEGIN DESCRIPTION:
Bee Caves Creek 11.0
END DESCRIPTION:
XS GIS Cut Line= 3
      1821874.97     13930925.02      1822275.00     13930725.00
      1822375.05     13930725.00
#Sta/Elev= 30
  4556.8 1951.75  4572.6 1950.05  4587.6 1946.10  4615.5 1942.09  4646.3 1936.11
  4668.6 1934.35  4681.8 1934.90  4721.7 1932.79  4779.1 1932.74  4793.9 1932.71
  4833.6 1932.70  4839.1 1932.41  4855.9 1929.32  4878.3 1929.11  4883.9 1928.62
  4914.6 1922.25  4923.0 1921.68  4981.7 1921.67  4983.7 1920.99  4984.2 1920.49
  4996.4 1920.99  5006.6 1921.30  5014.1 1923.29  5024.1 1923.98  5034.1 1923.65
  5044.1 1962.76  5054.1 1980.14  5067.5 1982.59  5074.1 1983.89  5104.1 1985.92
#Mann=8,-1,0
  4556.8     0.1       0  4572.6   0.035       0  4681.8    0.07       0
  4779.1   0.035       0  4793.9    0.07       0  4983.7    0.05       0
  4996.4    0.07       0  5067.5     0.1       0
Bank Sta=4983.7,4996.4
Exp/Cntr=0.3,0.1

Type RM Length L Ch R = 1,4628,459,459,459
BEGIN DESCRIPTION:
Bee Caves Creek 10.0
END DESCRIPTION:
XS GIS Cut Line= 3
      1821824.96     13931125.00      1822125.00     13931125.00
      1822325.00     13931075.00
#Sta/Elev= 30
  4705.2 1964.17  4755.2 1959.45  4785.2 1952.41  4805.2 1949.17  4825.2 1943.88
  4855.2 1932.61  4875.2 1928.15  4905.2 1925.25  4925.2 1925.96  4935.2 1924.66
  4955.2 1920.50  4995.2 1916.47  5022.1 1916.20  5022.6 1915.70  5034.3 1915.70
  5034.8 1916.20  5046.5 1916.64  5064.5 1926.26  5069.7 1925.21  5077.4 1930.81
  5105.7 1944.25  5110.9 1945.14  5118.6 1948.16  5139.2 1952.96  5147.0 1957.05
  5152.1 1957.51  5159.9 1960.76  5180.5 1963.60  5188.2 1965.92  5211.4 1967.81
#Mann=3,-1,0
  4705.2     0.1       0  5022.1    0.05       0  5034.8     0.1       0
Bank Sta=5022.1,5034.8
Exp/Cntr=0.3,0.1

Type RM Length L Ch R = 1,4169,487,487,487
BEGIN DESCRIPTION:
Bee Caves Creek 9.0
END DESCRIPTION:
XS GIS Cut Line= 3
      1821825.02     13931475.01      1822025.00     13931525.00
      1822324.97     13931525.00
#Sta/Elev= 30
  4789.3 1963.04  4812.5 1961.63  4830.5 1958.15  4840.8 1957.04  4882.0 1950.35
  4889.8 1947.44  4894.9 1946.89  4913.0 1934.75  4923.3 1922.70  4931.0 1920.11
  4952.4 1918.93  4972.2 1919.34  4985.1 1918.67  4992.9 1915.03  4997.9 1915.03
  4999.0 1912.76  4999.5 1912.26  5011.3 1912.26  5011.8 1912.76  5055.4 1915.35
  5065.4 1921.02  5075.4 1925.03  5135.4 1927.68  5145.4 1929.13  5155.4 1931.19
  5179.4 1939.00  5235.4 1961.55  5285.4 1978.03  5292.9 1980.35  5295.4 1980.35
#Mann=5,-1,0
  4789.3     0.1       0  4952.4    0.07       0  4999.0    0.05       0
  5011.8    0.07       0  5179.4     0.1       0
Bank Sta=4999,5011.8
Exp/Cntr=0.3,0.1

Type RM Length L Ch R = 1,3682,429,429,429
BEGIN DESCRIPTION:
Bee Caves Creek 8.0
END DESCRIPTION:
XS GIS Cut Line= 3
      1821624.98     13931975.00      1821925.00     13931975.00
      1822274.98     13931975.00
#Sta/Elev= 30
  4695.7 1962.61  4705.7 1961.39  4735.7 1953.91  4795.7 1944.87  4825.7 1939.25
  4865.7 1933.69  4895.7 1930.90  4905.7 1930.66  4935.7 1927.17  4955.7 1926.10
  4965.7 1924.42  4971.8 1922.18  4993.2 1912.83  5039.3 1911.89  5039.8 1911.39
  5051.6 1911.39  5052.1 1911.89  5085.7 1913.38  5095.7 1915.07  5115.7 1916.94
  5125.7 1919.19  5135.7 1920.36  5185.7 1922.98  5205.7 1927.01  5219.9 1933.25
  5245.7 1946.58  5255.7 1952.85  5275.7 1961.60  5295.7 1969.30  5345.7 1976.24
#Mann=5,-1,0
  4695.7     0.1       0  4971.8    0.07       0  5039.3    0.05       0
  5052.1    0.07       0  5219.9     0.1       0
Bank Sta=5039.3,5052.1
Exp/Cntr=0.3,0.1

Type RM Length L Ch R = 1,3253,467,467,467
BEGIN DESCRIPTION:
Bee Caves Creek 7.0
END DESCRIPTION:
XS GIS Cut Line= 3
      1821625.03     13932524.99      1821925.00     13932375.00
      1822224.97     13932175.02
#Sta/Elev= 30
  4664.6 1966.29  4700.9 1960.39  4709.3 1956.29  4745.6 1945.34  4784.8 1931.16
  4807.1 1925.88  4946.9 1921.80  4963.6 1918.77  4969.7 1918.96  4977.6 1914.37
  4986.0 1907.54  4990.7 1906.73  4991.2 1906.23  5003.6 1906.73  5028.5 1909.81
  5036.0 1912.69  5043.5 1913.48  5172.7 1916.33  5193.8 1918.77  5202.8 1921.46
  5208.8 1921.11  5218.5 1927.05  5223.8 1931.21  5229.8 1929.73  5238.8 1937.70
  5244.9 1935.12  5259.9 1947.92  5274.9 1951.94  5332.0 1962.84  5360.5 1965.76
#Mann=5,-1,0
  4664.6     0.1       0  4969.7    0.07       0  4990.7    0.05       0
  5003.6    0.07       0  5218.5     0.1       0
Bank Sta=4990.7,5003.6
Exp/Cntr=0.3,0.1

Type RM Length L Ch R = 1,2786,444,444,444
BEGIN DESCRIPTION:
Bee Caves Creek 6.0
END DESCRIPTION:
XS GIS Cut Line= 3
      1821825.01     13932974.99      1821975.00     13932825.00
      1822374.98     13932325.02
#Sta/Elev= 30
  4788.5 1966.92  4830.9 1963.59  4845.0 1957.61  4873.3 1933.99  4894.5 1920.52
  4929.9 1910.11  4958.2 1905.05  4972.3 1898.85  4980.0 1898.26  4980.5 1897.76
  4992.9 1898.26  4997.1 1904.06  5043.0 1902.43  5071.8 1904.05  5107.1 1911.63
  5164.7 1912.34  5171.1 1915.02  5179.1 1914.37  5185.5 1919.15  5199.9 1917.98
  5206.3 1920.35  5214.3 1920.08  5240.8 1916.03  5299.2 1917.46  5348.8 1925.54
  5427.2 1932.31  5454.1 1937.20  5524.0 1949.68  5604.9 1964.95  5640.9 1968.20
#Mann=6,-1,0
  4788.5     0.1       0  4980.0    0.05       0  4992.9     0.1       0
  5240.8   0.035       0  5454.1    0.07       0  5524.0     0.1       0
Bank Sta=4980,4992.9
Exp/Cntr=0.3,0.1

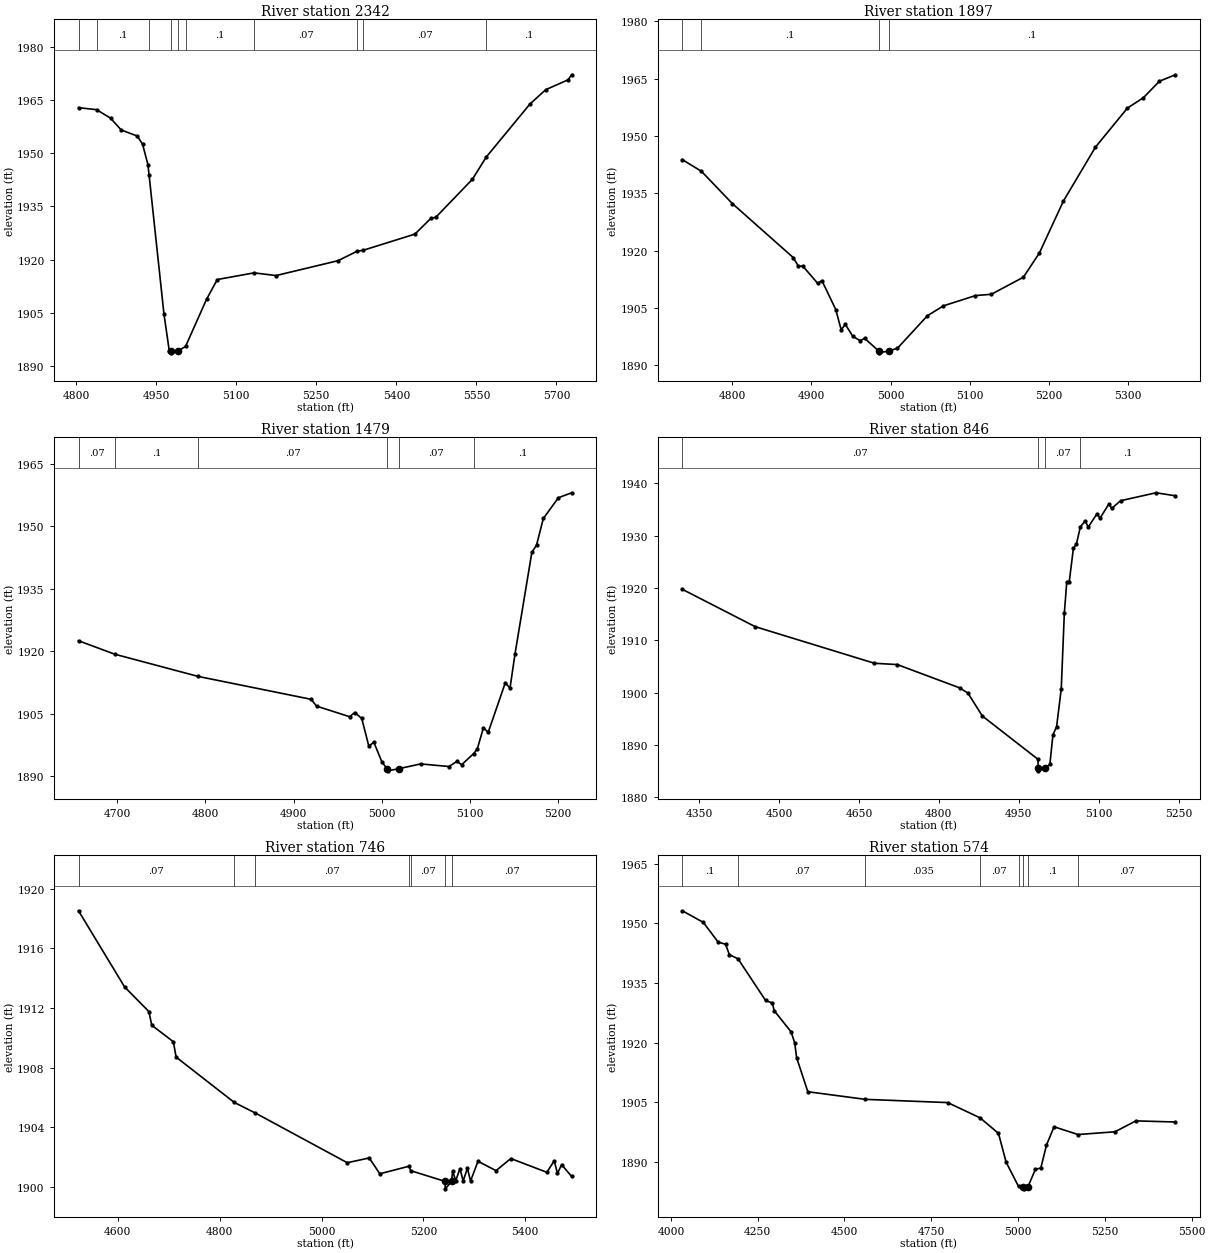
Type RM Length L Ch R = 1,2342,445,445,445
BEGIN DESCRIPTION:
Bee Caves Creek 5.0
END DESCRIPTION:
XS GIS Cut Line= 4
      1822275.00     13933224.98      1822275.00     13933025.00
      1822275.00     13932825.00      1822469.49     13932338.74
#Sta/Elev= 30
  4804.7 1962.84  4838.4 1962.29  4864.7 1959.89  4884.7 1956.55  4914.7 1954.85
  4924.7 1952.56  4934.7 1946.79  4936.8 1943.99  4964.7 1904.75  4974.7 1894.29
  4978.2 1894.22  4978.7 1893.72  4991.2 1894.22  5005.2 1895.53  5044.7 1908.87
  5064.7 1914.39  5133.5 1916.27  5174.7 1915.51  5290.8 1919.70  5326.6 1922.37
  5338.0 1922.64  5434.9 1927.20  5464.5 1931.61  5473.9 1931.93  5542.6 1942.67
  5568.5 1948.93  5650.3 1963.87  5679.9 1967.92  5721.7 1970.69  5728.4 1972.12
#Mann=10,-1,0
  4804.7    0.07       0  4838.4     0.1       0  4936.8    0.07       0
  4978.2    0.05       0  4991.2    0.07       0  5005.2     0.1       0
  5133.5    0.07       0  5326.6   0.035       0  5338.0    0.07       0
  5568.5     0.1       0
Bank Sta=4978.2,4991.2
Exp/Cntr=0.3,0.1

Type RM Length L Ch R = 1,1897,418,418,418
BEGIN DESCRIPTION:
Bee Caves Creek 4.0
END DESCRIPTION:
XS GIS Cut Line= 3
      1822575.02     13933124.96      1822675.00     13932875.00
      1822725.00     13932524.97
#Sta/Elev= 30
  4736.9 1943.85  4761.1 1940.78  4800.1 1932.34  4876.9 1918.23  4883.6 1915.92
  4889.0 1916.01  4907.8 1911.48  4913.2 1912.18  4930.7 1904.62  4937.5 1899.33
  4942.8 1900.72  4952.3 1897.58  4961.7 1896.45  4967.1 1897.10  4984.8 1893.78
  4985.3 1893.28  4997.8 1893.78  5008.6 1894.48  5046.5 1903.00  5066.7 1905.58
  5107.1 1908.26  5127.3 1908.61  5167.7 1913.08  5187.9 1919.42  5218.2 1933.00
  5258.7 1947.12  5299.1 1957.34  5319.3 1960.05  5339.5 1964.37  5359.7 1966.05
#Mann=4,-1,0
  4736.9   0.035       0  4761.1     0.1       0  4984.8    0.05       0
  4997.8     0.1       0
Bank Sta=4984.8,4997.8
Exp/Cntr=0.3,0.1

Type RM Length L Ch R = 1,1479,633,633,633
BEGIN DESCRIPTION:
Bee Caves Creek 3.0
END DESCRIPTION:
XS GIS Cut Line= 3
      1822877.66     13933125.01      1823054.42     13932810.38
      1823124.98     13932625.04
#Sta/Elev= 30
  4656.2 1922.51  4697.4 1919.27  4792.0 1913.94  4920.0 1908.45  4926.1 1906.82
  4963.7 1904.27  4969.4 1905.28  4977.4 1903.85  4985.4 1897.22  4991.1 1898.14
  5000.3 1893.41  5006.1 1891.78  5006.6 1891.28  5019.1 1891.78  5044.2 1892.94
  5076.3 1892.32  5085.3 1893.54  5090.7 1892.75  5104.4 1895.44  5108.4 1896.51
  5115.4 1901.65  5120.8 1900.52  5140.2 1912.44  5145.5 1911.09  5151.2 1919.37
  5170.3 1943.75  5175.6 1945.47  5183.3 1951.86  5200.4 1956.84  5215.4 1958.03
#Mann=6,-1,0
  4656.2    0.07       0  4697.4     0.1       0  4792.0    0.07       0
  5006.1    0.05       0  5019.1    0.07       0  5104.4     0.1       0
Bank Sta=5006.1,5019.1
Exp/Cntr=0.3,0.1

Type RM Length L Ch R = 1,846,100,100,100
BEGIN DESCRIPTION:
Bee Caves Creek 2.0
END DESCRIPTION:
XS GIS Cut Line= 4
      1822962.49     13933142.83      1823304.57     13933054.43
      1823622.86     13932865.36      1823715.68     13932685.53
#Sta/Elev= 30
  4318.3 1919.75  4455.2 1912.60  4679.1 1905.60  4722.0 1905.35  4838.9 1900.90
  4854.5 1899.90  4881.7 1895.51  4986.2 1887.22  4986.3 1885.52  4986.8 1885.02
  4999.3 1885.52  5008.4 1886.25  5014.2 1891.91  5021.1 1893.48  5029.8 1900.71
  5035.6 1915.22  5040.2 1921.19  5044.8 1921.19  5052.6 1927.59  5058.3 1928.41
  5065.7 1931.71  5074.8 1932.84  5080.4 1931.65  5096.9 1934.19  5102.6 1933.35
  5119.1 1936.06  5124.7 1935.24  5141.2 1936.70  5207.7 1938.22  5244.2 1937.64
#Mann=4,-1,0
  4318.3    0.07       0  4986.3    0.05       0  4999.3    0.07       0
  5065.7     0.1       0
Bank Sta=4986.3,4999.3
Exp/Cntr=0.3,0.1

Type RM Length L Ch R = 1,746,172,172,172
BEGIN DESCRIPTION:
Bee Caves Creek 1.1
END DESCRIPTION:
XS GIS Cut Line= 5
      1823222.59     13933152.82      1823526.65     13933027.84
      1823679.66     13932945.41      1823812.01     13932836.86
      1823990.04     13932602.03
#Sta/Elev= 30
  4522.8 1918.52  4613.2 1913.42  4661.1 1911.76  4666.6 1910.85  4709.1 1909.74
  4714.5 1908.71  4828.8 1905.67  4870.2 1904.96  5050.6 1901.63  5093.7 1901.95
  5114.5 1900.89  5172.5 1901.40  5174.9 1901.10  5242.6 1900.38  5243.1 1899.88
  5255.6 1900.38  5257.4 1901.07  5263.6 1900.43  5271.9 1901.23  5278.2 1900.41
  5286.5 1901.26  5292.7 1900.40  5307.3 1901.73  5342.7 1901.10  5371.8 1901.91
  5442.5 1900.99  5457.1 1901.76  5463.3 1900.91  5471.6 1901.50  5491.2 1900.71
#Mann=7,-1,0
  4522.8    0.07       0  4828.8   0.035       0  4870.2    0.07       0
  5172.5     0.1       0  5174.9    0.07       0  5242.6    0.05       0
  5255.6    0.07       0
Bank Sta=5242.6,5255.6
Exp/Cntr=0.3,0.1

Type RM Length L Ch R = 1,574,0,0,0
BEGIN DESCRIPTION:
Bee Caves Creek 1.0
END DESCRIPTION:
XS GIS Cut Line= 4
      1822896.42     13933369.61      1823761.42     13933095.17
      1823811.58     13933027.14      1824013.81     13932649.49
#Sta/Elev= 30
  4032.9 1953.17  4093.4 1950.25  4136.3 1945.28  4157.3 1944.78  4168.5 1942.14
  4193.4 1941.09  4272.7 1930.63  4292.3 1929.97  4297.5 1928.07  4346.1 1922.75
  4356.6 1920.01  4362.1 1916.26  4394.4 1907.69  4560.3 1905.77  4797.3 1904.96
  4890.4 1901.13  4943.6 1897.23  4965.5 1890.01  5001.4 1883.87  5015.3 1883.78
  5015.8 1883.28  5028.4 1883.78  5050.0 1888.21  5065.5 1888.50  5081.8 1894.26
  5103.7 1898.88  5172.6 1896.93  5279.2 1897.62  5339.3 1900.36  5453.3 1900.08
#Mann=8,-1,0
  4032.9     0.1       0  4193.4    0.07       0  4560.3   0.035       0
  4890.4    0.07       0  5001.4     0.1       0  5015.3    0.05       0
  5028.4     0.1       0  5172.6    0.07       0
Bank Sta=5015.3,5028.4
Exp/Cntr=0.3,0.1

Chan Stop Cuts=-1