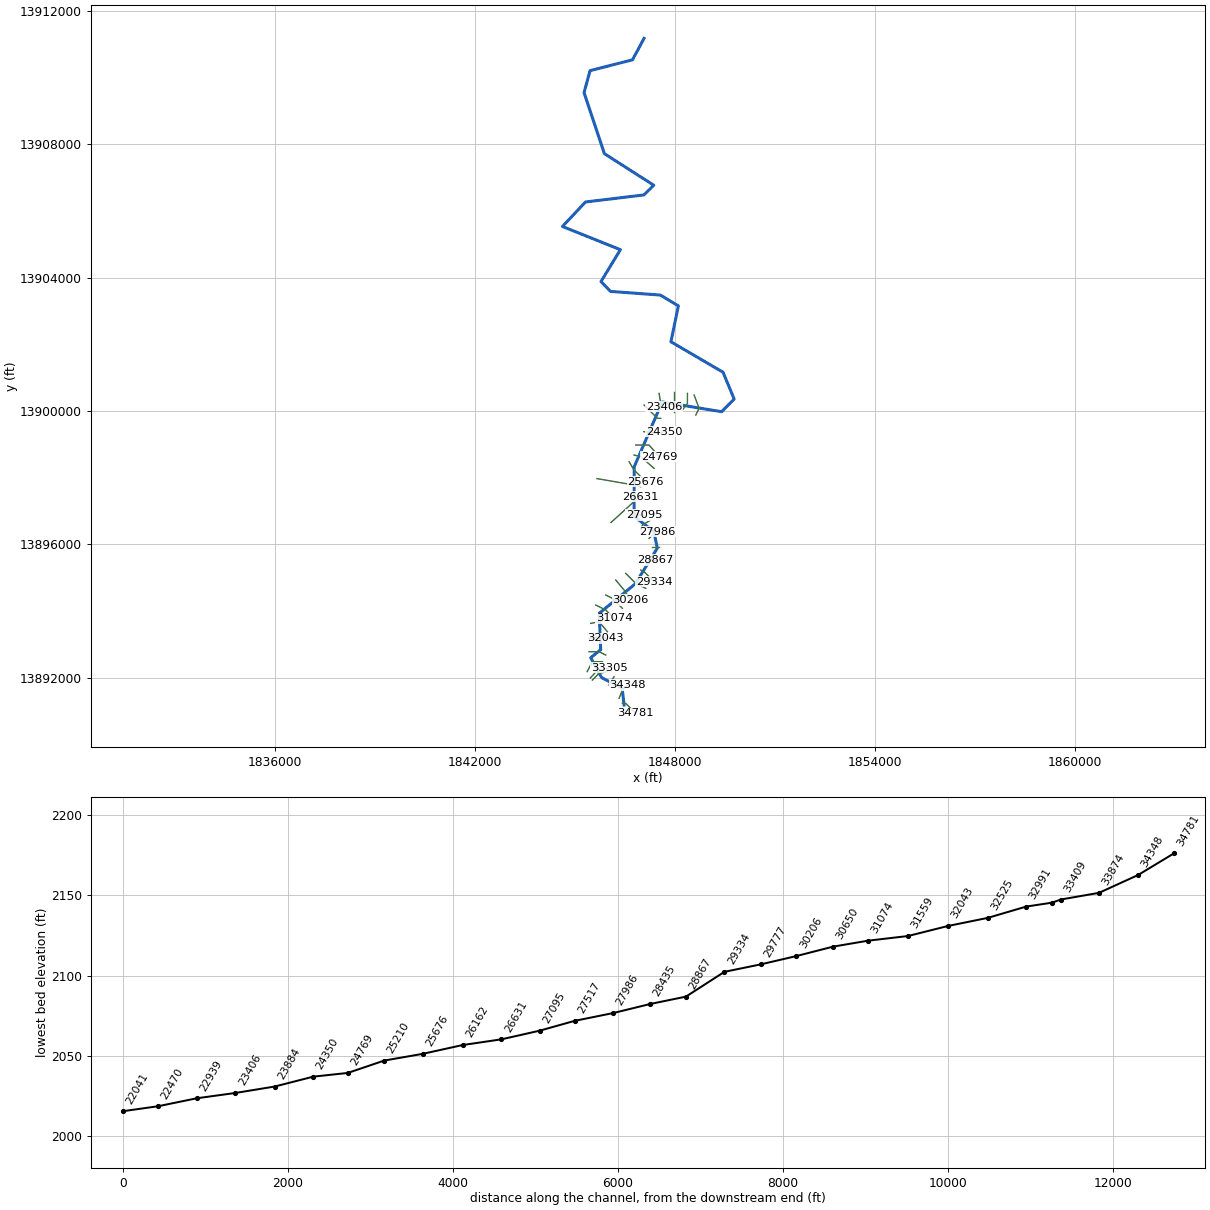
--- Buffalo Creek.prj (project) ---

Proj Title=Buffalo Creek Base Level Engineering
Current Plan=p01
Default Exp/Contr=0.3,0.1
English Units
Geom File=g01
Flow File=f01
Plan File=p01
Y Axis Title=Elevation
X Axis Title(PF)=Main Channel Distance
X Axis Title(XS)=Station
BEGIN DESCRIPTION:
Buffalo Creek
END DESCRIPTION:
DSS Export Rating Curves= 0
DSS Export Rating Curve Sorted= 0
DSS Export Volume Flow Curves= 0
DXF OffsetX= 0
DXF OffsetY= 0
DXF ScaleX= 1
DXF ScaleY= 10

--- Buffalo Creek.p01 (plan) ---

Plan Title=Multiple Run
Short Identifier=Multiple
Geom File=g01
Flow File=f01
Subcritical Flow
K Sum by GR= 0
Std Step Tol= 0.01
Critical Tol= 0.01
Num of Std Step Trials= 20
Max Error Tol= 0.3
Flow Tol Ratio= 0.001
Split Flow NTrial= 30
Split Flow Tol= 0.02
Split Flow Ratio= 0.02
Log Output Level= 0
Friction Slope Method= 1
Unsteady Friction Slope Method= 2
Unsteady Bridges Friction Slope Method= 1
Parabolic Critical Depth
Global Vel Dist=  1 , 1 , 1
Global Log Level= 0
CheckData=True
Encroach Param= -1, 0, 0, 0
BEGIN DESCRIPTION:
Multiple Run
END DESCRIPTION:

--- Buffalo Creek.f01 (steady flow) ---

Flow Title=Multiple
Number of Profiles=7
Profile Names=10-year,25-year,50-year,1pct_min,100-year,1pct_plu,500-year
River Rch & RM= Buffalo Creek,Reach-1,34781
     731    1216    1667    1106    2207    4404    3822
River Rch & RM= Buffalo Creek,Reach-1,32525
    1190    2034    2837    1913    3817    7615    6825
River Rch & RM= Buffalo Creek,Reach-1,26631
    1495    2593    3651    2480    4949    9874    8996
River Rch & RM= Buffalo Creek,Reach-1,19794
    2779    4966    7136    4936    9849   19651   18576
River Rch & RM= Buffalo Creek,Reach-1,14757
    3259    5861    8454    5868   11708   23360   22235
River Rch & RM= Buffalo Creek,Reach-1,10686
    3637    6564    9492    6601   13170   26278   25112
River Rch & RM= Buffalo Creek,Reach-1,3195
    3733    6741    9752    6784   13536   27008   25827
River Rch & RM= Buffalo Creek,Reach-1,777
    3809    6882    9960    6931   13830   27594   26405
Boundary for River Rch & Prof#=Buffalo Creek,Reach-1,1
Up Type=0
Dn Type=3
Dn Slope=0.005
Boundary for River Rch & Prof#=Buffalo Creek,Reach-1,2
Up Type=0
Dn Type=3
Dn Slope=0.005
Boundary for River Rch & Prof#=Buffalo Creek,Reach-1,3
Up Type=0
Dn Type=3
Dn Slope=0.005
Boundary for River Rch & Prof#=Buffalo Creek,Reach-1,4
Up Type=0
Dn Type=3
Dn Slope=0.005
Boundary for River Rch & Prof#=Buffalo Creek,Reach-1,5
Up Type=0
Dn Type=3
Dn Slope=0.005
Boundary for River Rch & Prof#=Buffalo Creek,Reach-1,6
Up Type=0
Dn Type=3
Dn Slope=0.005
Boundary for River Rch & Prof#=Buffalo Creek,Reach-1,7
Up Type=0
Dn Type=3
Dn Slope=0.005

--- Buffalo Creek.g01 (geometry) ---

Geom Title=Existing Conditions
Program Version=4.10

River Reach=Buffalo Creek   ,Reach-1
Reach XY= 30
        1846475.       13891175.      1846417.18     13891681.19
      1845801.16     13891997.86      1845474.21     13892595.33
      1845773.96     13892835.43      1845730.34     13893927.74
      1846808.36     13894808.32      1847472.74     13895880.94
      1847367.15     13896381.19      1846777.24     13896830.93
      1846778.83     13898323.42      1847618.66     13900266.98
      1849400.09     13899974.79      1849775.36     13900354.85
      1849441.81     13901158.67      1847879.99     13902072.45
      1848102.13     13903148.52       1847564.5     13903473.78
      1846068.83     13903582.76      1845783.02     13903878.31
      1846364.52      13904834.8      1844626.96     13905530.89
      1845318.45     13906265.76      1847069.07     13906477.24
      1847365.61     13906768.39      1845885.52     13907715.21
      1845274.91      13909545.1      1845454.96     13910205.71
      1846727.93     13910530.72        1847075.       13911175.

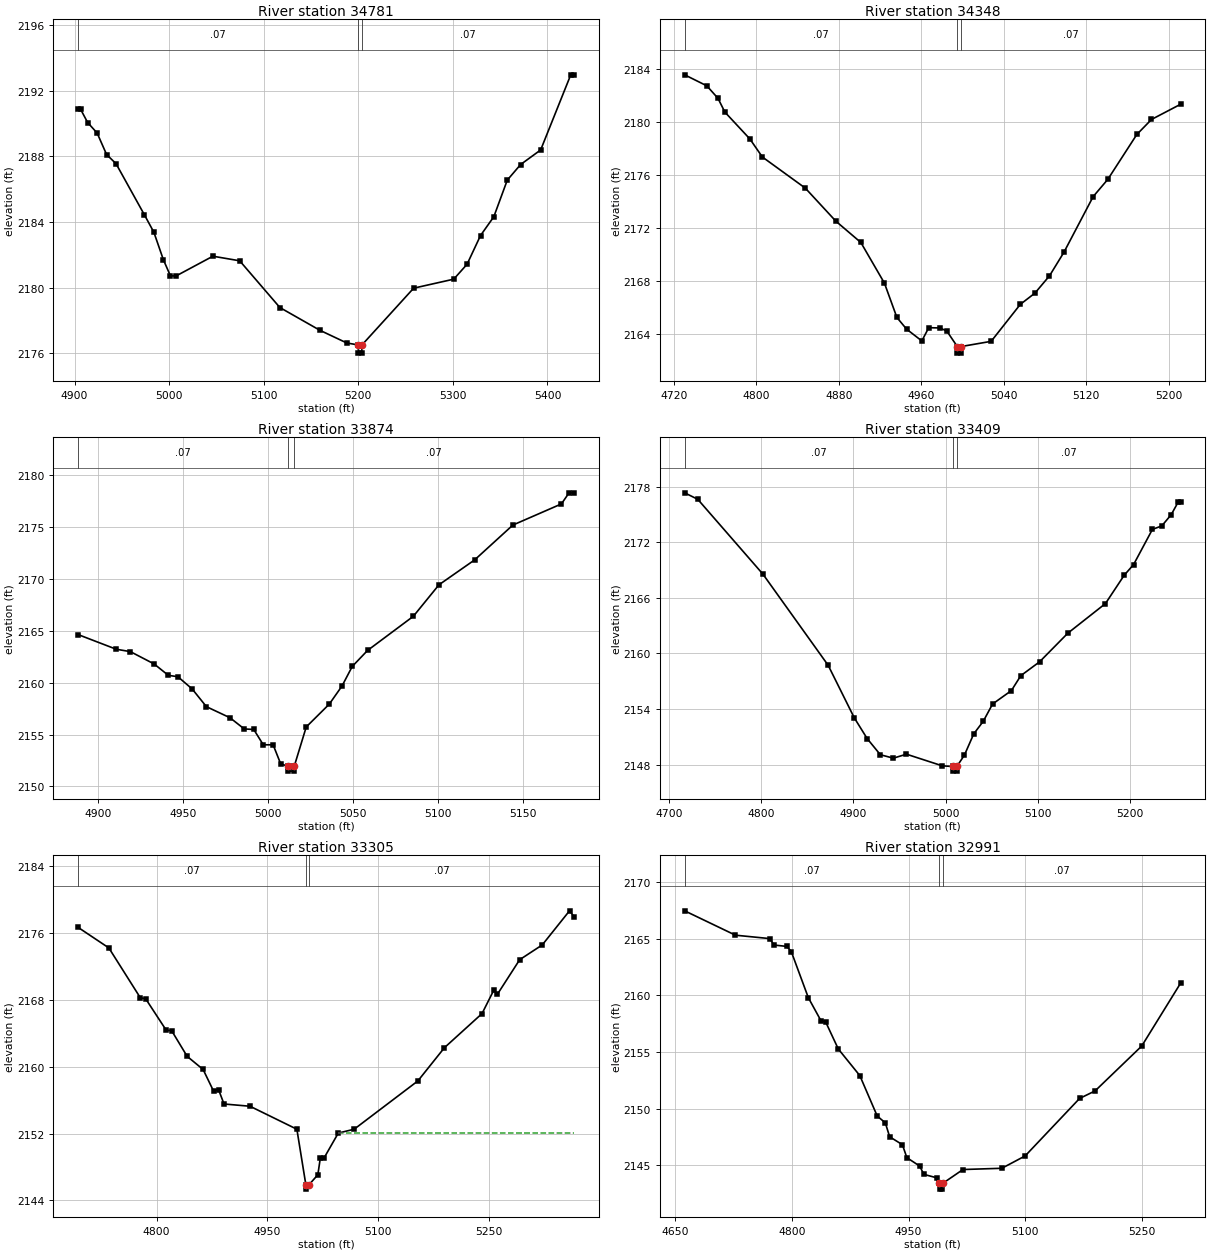
Type RM Length L Ch R = 1 ,34781   ,433,433,433
BEGIN DESCRIPTION:
Buffalo Creek 76.0
END DESCRIPTION:
XS GIS Cut Line= 3
      1846424.98       13891225.        1846525.       13891225.
      1846825.01     13890924.99
#Sta/Elev= 30
  4903.9 2190.87  4906.4 2190.87  4913.9 2190.06  4923.9 2189.42  4933.9 2188.11
  4943.9 2187.55  4973.9 2184.43  4983.9 2183.37  4993.9  2181.7  5001.4 2180.71
  5007.5 2180.71  5046.3 2181.91  5074.6 2181.63  5117.1 2178.78  5159.5 2177.39
  5187.8 2176.62  5199.9  2176.5  5200.2    2176  5203.7    2176  5203.9  2176.5
  5258.5 2179.96  5300.9 2180.51    5315 2181.42  5329.2 2183.17  5343.3 2184.32
  5357.5 2186.55  5371.6  2187.5  5392.8 2188.39  5424.6 2192.97  5428.2 2192.97
#Mann= 3 ,-1 , 0
  4903.9     .07       0  5199.9     .05       0  5203.9     .07       0
Bank Sta=5199.9,5203.9
XS Rating Curve= 0 ,0
Exp/Cntr=0.3,0.1

Type RM Length L Ch R = 1 ,34348   ,474,474,474
BEGIN DESCRIPTION:
Buffalo Creek 75.0
END DESCRIPTION:
XS GIS Cut Line= 3
      1846325.01     13891375.01        1846425.       13891625.
      1846575.02     13891775.02
#Sta/Elev= 30
  4730.3 2183.58  4751.8 2182.75  4762.6 2181.81  4769.3 2180.77  4793.6 2178.74
  4805.7 2177.38  4847.4 2175.03    4877 2172.54  4901.3 2170.93  4924.2 2167.86
  4936.3 2165.27  4945.7 2164.39  4960.5  2163.5  4967.2  2164.5    4978 2164.48
  4984.7 2164.25  4994.9 2163.08  4995.1 2162.58  4998.6 2162.58  4998.9 2163.08
  5027.8 2163.47  5056.1 2166.26  5070.3 2167.11  5084.4 2168.41  5098.5  2170.2
  5126.8 2174.39    5141 2175.69  5169.2 2179.08  5183.4 2180.21  5211.7 2181.36
#Mann= 3 ,-1 , 0
  4730.3     .07       0  4994.9     .05       0  4998.9     .07       0
Bank Sta=4994.9,4998.9
XS Rating Curve= 0 ,0
Exp/Cntr=0.3,0.1

Type RM Length L Ch R = 1 ,33874   ,465,465,465
BEGIN DESCRIPTION:
Buffalo Creek 74.0
END DESCRIPTION:
XS GIS Cut Line= 3
        1846025.       13891775.        1846075.       13891875.
      1846175.01     13892025.02
#Sta/Elev= 30
  4888.2 2164.64  4910.6 2163.23  4918.9    2163  4932.9 2161.81  4941.3 2160.71
  4946.9 2160.58  4955.3  2159.4  4963.7 2157.69  4977.6 2156.62    4986 2155.54
  4991.6 2155.49  4997.2 2154.01    5003 2154.01  5007.5 2152.15  5011.5 2151.97
  5011.8 2151.47  5015.3 2151.47  5015.5 2151.97  5022.5 2155.73  5036.1 2157.94
  5043.6 2159.69  5049.6 2161.57  5058.6 2163.11  5085.6 2166.41  5100.7 2169.45
  5121.7 2171.85  5144.2 2175.21  5172.8 2177.25  5177.3 2178.32  5180.3 2178.32
#Mann= 3 ,-1 , 0
  4888.2     .07       0  5011.5     .05       0  5015.5     .07       0
Bank Sta=5011.5,5015.5
XS Rating Curve= 0 ,0
Exp/Cntr=0.3,0.1

Type RM Length L Ch R = 1 ,33409   ,104,104,104
BEGIN DESCRIPTION:
Buffalo Creek 73.0
END DESCRIPTION:
XS GIS Cut Line= 3
      1845524.97     13891924.97        1845725.       13892125.
      1845974.96     13892174.99
#Sta/Elev= 30
  4717.1 2177.35  4731.3 2176.65    4802 2168.56  4872.7 2158.72    4901 2153.05
  4915.1 2150.79  4929.3 2149.06  4943.4 2148.69  4957.6 2149.12  4996.5 2147.86
  5008.2 2147.79  5008.4 2147.29  5011.9 2147.29  5012.2 2147.79  5020.4 2149.01
  5030.6 2151.32  5040.8 2152.66    5051 2154.54  5071.4 2155.99  5081.6  2157.6
    5102  2159.1  5132.6 2162.19  5173.4 2165.39  5193.8 2168.46  5203.9  2169.6
  5224.3  2173.4  5234.5 2173.78  5244.7 2174.99  5252.4 2176.38  5254.9 2176.38
#Mann= 3 ,-1 , 0
  4717.1     .07       0  5008.2     .05       0  5012.2     .07       0
Bank Sta=5008.2,5012.2
XS Rating Curve= 0 ,0
Exp/Cntr=0.3,0.1

Type RM Length L Ch R = 1 ,33305   ,314,314,314
BEGIN DESCRIPTION:
Buffalo Creek 72.1
END DESCRIPTION:
XS GIS Cut Line= 4
      1845463.63     13891987.58      1845634.21     13892173.78
       1845690.2     13892224.56      1846027.41     13892290.96
#Sta/Elev= 30
  4693.8 2176.68  4735.3 2174.23  4777.9 2168.27  4785.2 2168.14    4813 2164.38
  4820.4 2164.32  4841.4 2161.25    4863 2159.68  4877.1  2157.1  4883.9 2157.27
  4891.3 2155.55  4926.5 2155.28    4990 2152.53  5002.2 2145.86  5002.4 2145.36
  5006.2 2145.86  5018.4 2147.08  5021.8  2149.1  5026.9  2149.1  5046.1 2152.07
  5067.6 2152.53  5153.9 2158.31  5189.9 2162.29  5240.8 2166.37  5256.6 2169.15
  5261.7 2168.69  5291.8 2172.82  5322.4 2174.59  5359.3 2178.67  5365.6 2177.96
#Mann= 3 ,-1 , 0
  4693.8     .07       0  5002.2     .05       0  5006.2     .07       0
#XS Ineff= 2 , 0
                         5045.95         2152.06
Permanent Ineff=
       F       F
Bank Sta=5002.2,5006.2
XS Rating Curve= 0 ,0
Exp/Cntr=0.3,0.1

Type RM Length L Ch R = 1 ,32991   ,466,466,466
BEGIN DESCRIPTION:
Buffalo Creek 72.0
END DESCRIPTION:
XS GIS Cut Line= 3
      1845367.81     13892175.72        1845525.       13892475.
      1845824.95       13892475.
#Sta/Elev= 30
    4662 2167.47  4727.3 2165.32  4771.4 2165.02    4777 2164.45  4793.4 2164.33
  4799.1 2163.88  4821.1  2159.8  4837.5 2157.75  4843.2 2157.69  4859.6 2155.28
  4887.3 2152.93  4909.7 2149.36  4920.1 2148.76  4925.7 2147.53  4942.1 2146.83
  4947.8 2145.69  4964.2 2144.95  4969.8 2144.21  4986.2 2143.91  4989.8 2143.41
  4990.1 2142.91  4993.6 2142.91  4993.8 2143.41    5020 2144.64    5070 2144.75
    5100 2145.84    5170 2150.91    5190 2151.58    5250 2155.54    5300 2161.09
#Mann= 3 ,-1 , 0
    4662     .07       0  4989.8     .05       0  4993.8     .07       0
Bank Sta=4989.8,4993.8
XS Rating Curve= 0 ,0
Exp/Cntr=0.3,0.1

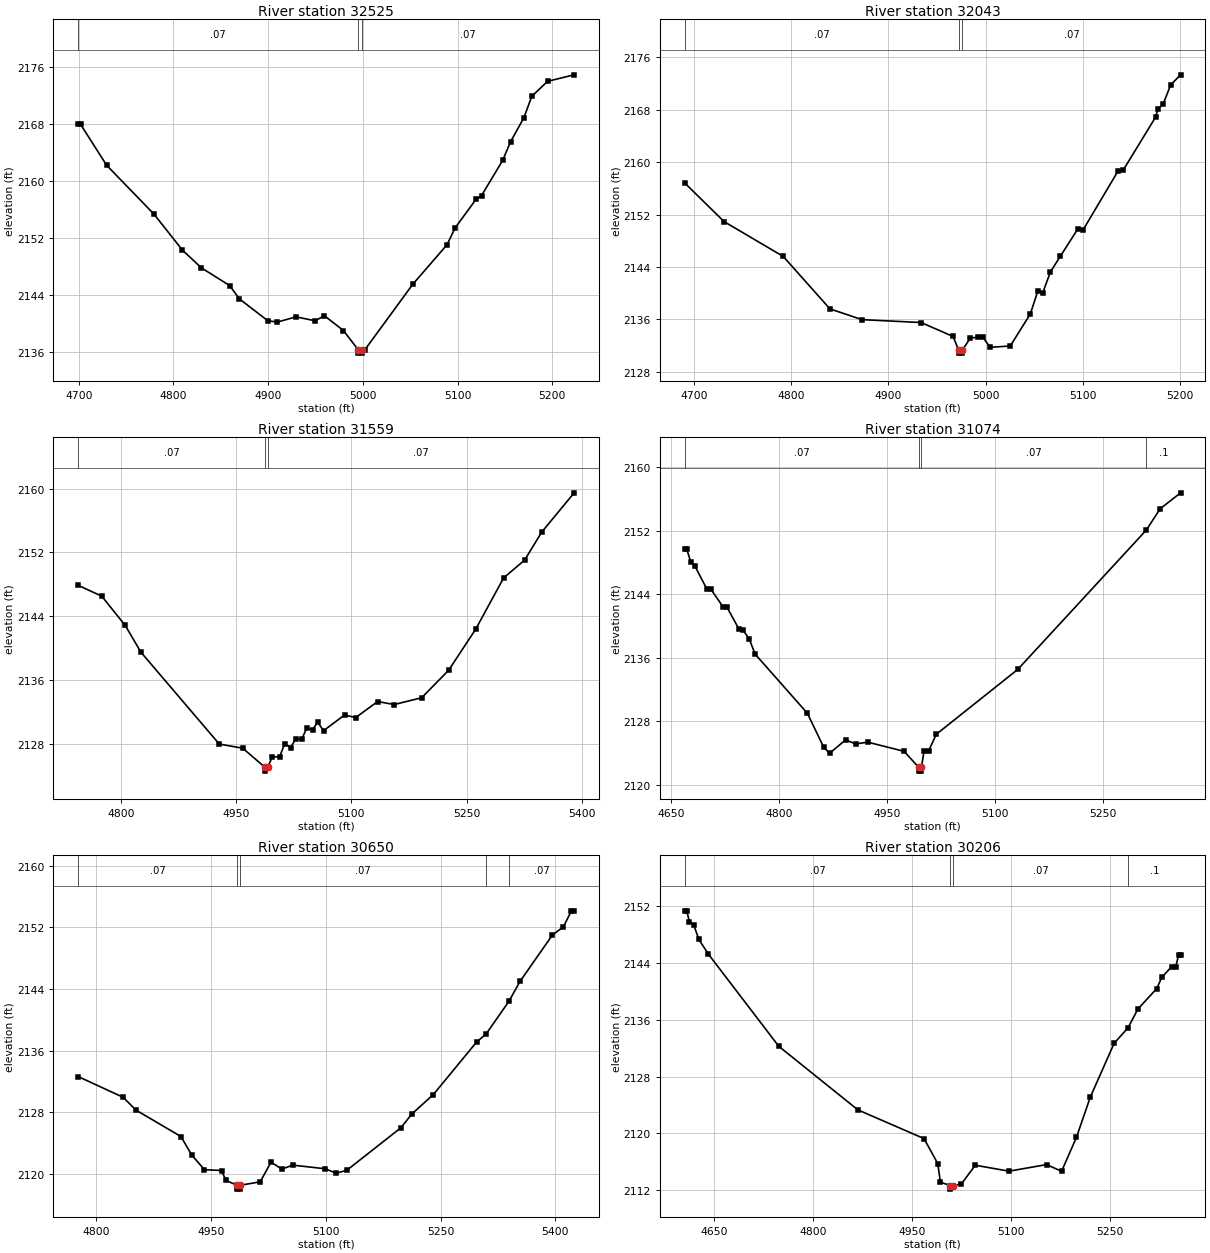
Type RM Length L Ch R = 1 ,32525   ,482,482,482
BEGIN DESCRIPTION:
Buffalo Creek 71.0
END DESCRIPTION:
XS GIS Cut Line= 3
      1845425.03       13892775.        1845725.       13892775.
      1845925.02     13892674.99
#Sta/Elev= 30
  4699.5 2167.98    4702 2167.98  4729.5 2162.24  4779.5 2155.38  4809.5 2150.34
  4829.5 2147.85  4859.5 2145.35  4869.5 2143.51  4899.5 2140.44  4909.5 2140.23
  4929.5 2140.97  4949.5 2140.42  4959.5 2141.12  4979.5 2139.05    4995 2136.38
  4995.2 2135.88  4998.7 2135.88    4999 2136.38  5002.3 2136.38  5052.6 2145.52
  5088.9 2151.09  5097.3 2153.43  5119.7  2157.5  5125.3 2157.99  5147.6 2162.92
    5156 2165.55    5170 2168.91  5178.4 2171.92  5195.1 2174.02  5223.1 2174.93
#Mann= 3 ,-1 , 0
  4699.5     .07       0    4995     .05       0    4999     .07       0
Bank Sta=4995,4999
XS Rating Curve= 0 ,0
Exp/Cntr=0.3,0.1

Type RM Length L Ch R = 1 ,32043   ,484,484,484
BEGIN DESCRIPTION:
Buffalo Creek 70.0
END DESCRIPTION:
XS GIS Cut Line= 3
      1845425.02       13893175.        1845725.       13893225.
      1845925.03     13893174.99
#Sta/Elev= 30
  4690.4 2156.82  4730.9 2150.92  4791.8  2145.6  4839.9 2137.59  4872.9 2135.95
  4933.7 2135.51  4966.6 2133.38  4972.2 2131.34  4972.5 2130.84    4976 2130.84
  4976.2 2131.34  4984.4 2133.15    4992 2133.26  4997.1 2133.26  5004.8 2131.73
  5025.4 2131.93  5046.1 2136.83  5053.8 2140.35  5058.9 2140.07  5066.7 2143.22
    5077 2145.64    5095 2149.81  5100.2 2149.61  5136.2 2158.61  5141.4 2158.72
  5174.9 2166.85  5177.5 2168.18  5182.6  2168.8  5190.4 2171.78  5200.7 2173.32
#Mann= 3 ,-1 , 0
  4690.4     .07       0  4972.2     .05       0  4976.2     .07       0
Bank Sta=4972.2,4976.2
XS Rating Curve= 0 ,0
Exp/Cntr=0.3,0.1

Type RM Length L Ch R = 1 ,31559   ,485,485,485
BEGIN DESCRIPTION:
Buffalo Creek 69.0
END DESCRIPTION:
XS GIS Cut Line= 3
      1845474.96     13893624.99        1845725.       13893675.
        1845975.     13893375.01
#Sta/Elev= 30
  4744.4 2147.87    4775 2146.52  4805.6 2142.85    4826  2139.5    4928 2127.99
  4958.6 2127.47  4987.2  2125.1  4987.4  2124.6  4991.2  2125.1  4996.8 2126.37
  5006.6 2126.41  5013.1 2128.02  5020.9 2127.54  5027.4 2128.66  5035.2 2128.59
  5041.7 2129.94  5049.5  2129.8    5056 2130.72  5063.8 2129.67  5091.2 2131.64
  5105.5  2131.3  5134.1 2133.32  5155.6 2132.94  5191.4 2133.79  5226.5 2137.23
  5261.7 2142.37  5298.1  2148.8  5325.5 2151.04  5347.6 2154.53  5389.9 2159.46
#Mann= 3 ,-1 , 0
  4744.4     .07       0  4987.2     .05       0  4991.2     .07       0
Bank Sta=4987.2,4991.2
XS Rating Curve= 0 ,0
Exp/Cntr=0.3,0.1

Type RM Length L Ch R = 1 ,31074   ,424,424,424
BEGIN DESCRIPTION:
Buffalo Creek 68.0
END DESCRIPTION:
XS GIS Cut Line= 3
      1845624.98     13894175.01        1845925.       13894025.
      1846175.01     13893774.99
#Sta/Elev= 30
  4668.7  2149.7  4671.5  2149.7  4677.1 2148.08  4682.7 2147.58  4699.5 2144.65
  4705.1 2144.62  4721.8 2142.43  4727.4 2142.37  4744.2 2139.58  4749.8 2139.46
  4758.2 2138.39  4766.6 2136.44  4839.2 2128.98  4861.6 2124.74    4870 2123.94
  4892.3 2125.63  4906.3 2125.12  4923.1 2125.34  4973.4 2124.19  4993.7 2122.19
    4994 2121.69  4997.5 2121.69  4997.7 2122.19  5001.3 2124.26  5007.7 2124.26
  5018.3 2126.34  5131.4 2134.51  5310.1 2152.09  5329.4 2154.78  5357.7 2156.78
#Mann= 4 ,-1 , 0
  4668.7     .07       0  4993.7     .05       0  4997.7     .07       0
  5310.1      .1       0
Bank Sta=4993.7,4997.7
XS Rating Curve= 0 ,0
Exp/Cntr=0.3,0.1

Type RM Length L Ch R = 1 ,30650   ,444,444,444
BEGIN DESCRIPTION:
Buffalo Creek 67.0
END DESCRIPTION:
XS GIS Cut Line= 3
      1845924.99     13894475.01        1846125.       13894375.
      1846425.01     13894074.99
#Sta/Elev= 30
  4776.6 2132.61  4835.3 2129.92  4852.1 2128.25  4910.8 2124.82  4924.8 2122.43
  4941.5 2120.51  4963.9  2120.4  4969.5 2119.11  4984.2 2118.48  4984.5 2117.98
    4988 2117.98  4988.2 2118.48  5014.4 2118.93  5028.5 2121.49  5042.6 2120.58
  5056.8  2121.1  5099.2 2120.63  5113.4 2120.05  5127.5 2120.43  5198.2 2125.96
  5212.4 2127.74  5240.6 2130.28  5297.2 2137.12  5309.6 2138.16  5339.3  2142.4
  5353.8 2144.99  5396.2 2151.03  5410.3 2152.07    5421 2154.16  5424.5 2154.16
#Mann= 5 ,-1 , 0
  4776.6     .07       0  4984.2     .05       0  4988.2     .07       0
  5309.6      .1       0  5339.3     .07       0
Bank Sta=4984.2,4988.2
XS Rating Curve= 0 ,0
Exp/Cntr=0.3,0.1

Type RM Length L Ch R = 1 ,30206   ,429,429,429
BEGIN DESCRIPTION:
Buffalo Creek 66.0
END DESCRIPTION:
XS GIS Cut Line= 3
      1846225.01     13894924.99        1846475.       13894625.
      1846675.02     13894324.97
#Sta/Elev= 30
  4605.3 2151.35  4608.5 2151.35  4612.5 2149.78    4619 2149.37  4626.8 2147.31
  4641.1 2145.26  4747.8 2132.26  4867.6  2123.3  4967.8 2119.25  4988.6 2115.73
  4992.6 2113.12  5007.3 2112.63  5007.6 2112.13  5011.3 2112.63  5024.3 2112.85
  5045.4  2115.5  5096.5 2114.66  5153.5 2115.59  5176.1 2114.64  5198.6 2119.42
  5219.6 2125.09  5255.7 2132.68  5276.7 2134.86  5291.8 2137.52  5320.3  2140.4
  5327.8 2141.96  5342.8 2143.48  5348.8  2143.4  5353.4 2145.12  5356.4 2145.12
#Mann= 4 ,-1 , 0
  4605.3     .07       0  5007.3     .05       0  5011.3     .07       0
  5276.7      .1       0
Bank Sta=5007.3,5011.3
XS Rating Curve= 0 ,0
Exp/Cntr=0.3,0.1

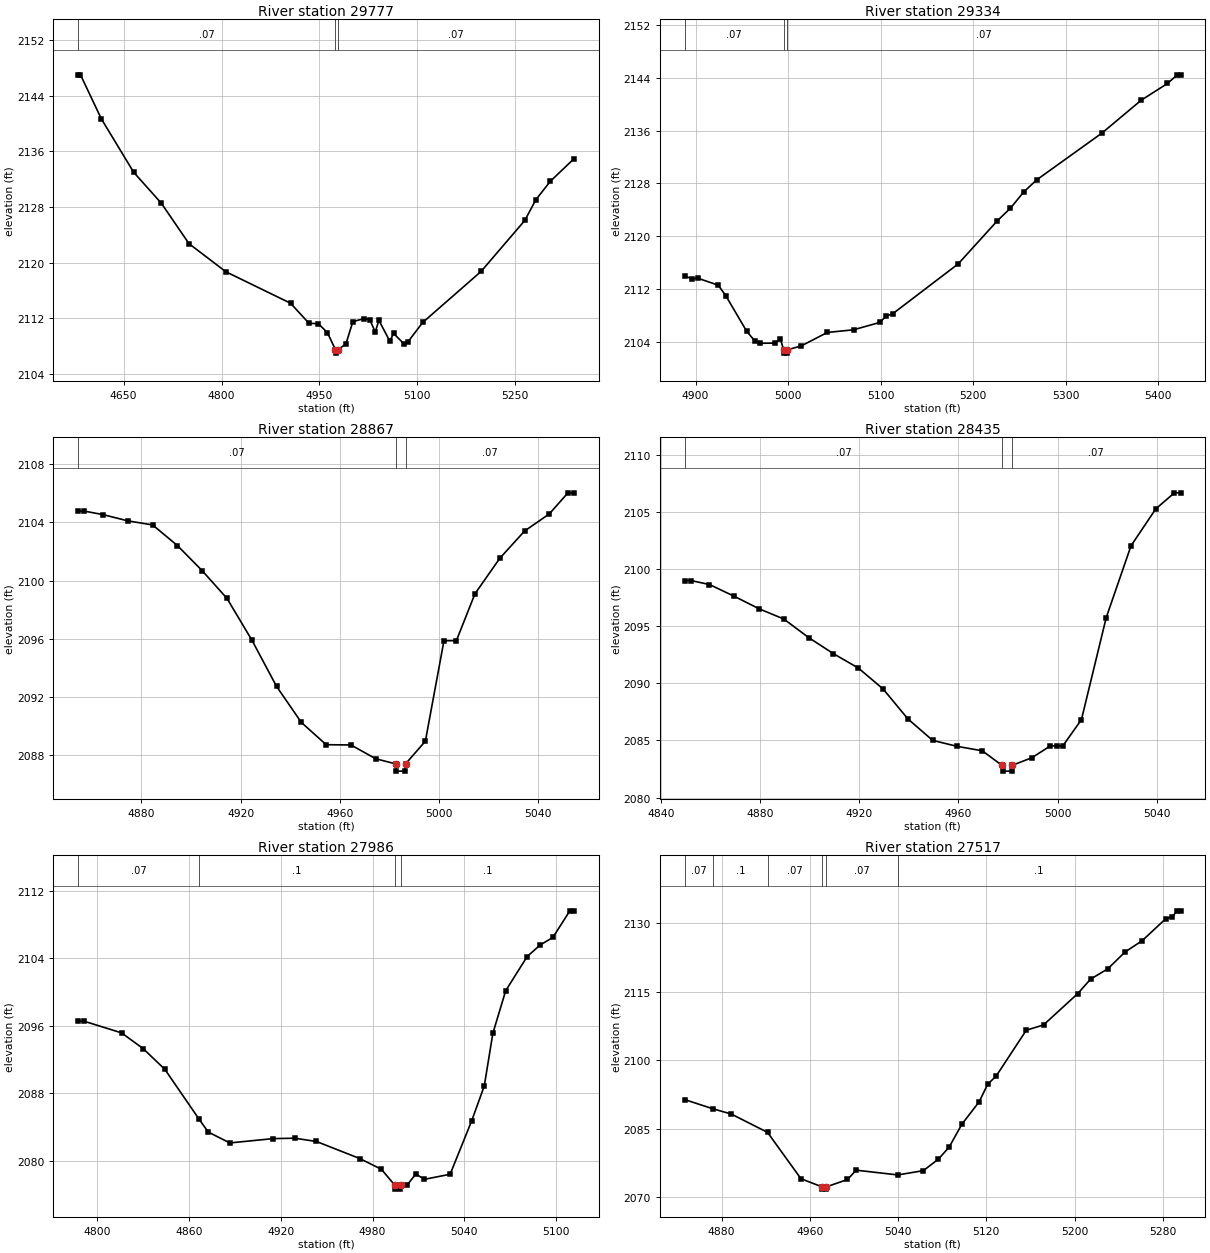
Type RM Length L Ch R = 1 ,29777   ,443,443,443
BEGIN DESCRIPTION:
Buffalo Creek 65.0
END DESCRIPTION:
XS GIS Cut Line= 3
      1846524.99     13895125.01        1846825.       13894825.
      1847125.02     13894674.99
#Sta/Elev= 30
  4580.5 2147.03    4584 2147.03  4615.9  2140.7  4665.4 2133.02  4707.8 2128.56
  4750.2 2122.74  4806.8 2118.69  4905.8 2114.17  4934.1 2111.27  4948.2 2111.24
  4962.3 2109.93  4974.5 2107.49  4974.7 2106.99  4978.5 2107.49  4990.6 2108.32
  5001.2 2111.52  5018.7 2111.97  5027.1  2111.8  5035.5 2110.03  5041.1 2111.71
  5057.9 2108.69  5063.5 2109.83  5080.2 2108.26  5085.8 2108.64  5108.2  2111.4
  5197.6 2118.74  5264.7 2126.09  5281.5 2129.06  5303.8 2131.72  5340.2 2134.98
#Mann= 3 ,-1 , 0
  4580.5     .07       0  4974.5     .05       0  4978.5     .07       0
Bank Sta=4974.5,4978.5
XS Rating Curve= 0 ,0
Exp/Cntr=0.3,0.1

Type RM Length L Ch R = 1 ,29334   ,467,467,467
BEGIN DESCRIPTION:
Buffalo Creek 64.0
END DESCRIPTION:
XS GIS Cut Line= 3
      1846974.99       13895225.        1847075.       13895175.
      1847375.02     13894874.98
#Sta/Elev= 30
  4888.2 2113.97  4896.6 2113.57  4902.2 2113.67  4924.5  2112.6  4932.9 2110.95
  4955.3 2105.61  4963.7 2104.23  4969.3 2103.81    4986 2103.84  4991.6 2104.49
  4995.2 2102.82  4995.5 2102.32    4999 2102.32  4999.2 2102.82  5014.2 2103.41
  5042.4 2105.45  5070.7 2105.85    5099 2106.96  5106.1 2107.94  5113.1 2108.28
  5183.9 2115.83  5226.3 2122.37  5240.4 2124.26  5254.6  2126.7  5268.7 2128.54
  5339.4 2135.64  5381.8 2140.61  5410.1 2143.13  5420.7 2144.44  5424.3 2144.44
#Mann= 3 ,-1 , 0
  4888.2     .07       0  4995.2     .05       0  4999.2     .07       0
Bank Sta=4995.2,4999.2
XS Rating Curve= 0 ,0
Exp/Cntr=0.3,0.1

Type RM Length L Ch R = 1 ,28867   ,432,432,432
BEGIN DESCRIPTION:
Buffalo Creek 63.0
END DESCRIPTION:
XS GIS Cut Line= 3
      1847224.96       13895525.        1847375.       13895525.
      1847424.96       13895525.
#Sta/Elev= 27
  4854.5 2104.78    4857 2104.78  4864.5 2104.54  4874.5 2104.11  4884.5 2103.83
  4894.5 2102.41  4904.5 2100.68  4914.5 2098.77  4924.5 2095.91  4934.5 2092.71
  4944.5 2090.23  4954.5  2088.7  4964.5 2088.68  4974.5 2087.73  4982.5 2087.38
  4982.8 2086.88  4986.3 2086.88  4986.5 2087.38  4994.5 2088.94    5002 2095.86
    5007 2095.86  5014.5 2099.09  5024.5 2101.53  5034.5 2103.41  5044.5 2104.59
    5052 2106.04  5054.5 2106.04
#Mann= 3 ,-1 , 0
  4854.5     .07       0  4982.5     .05       0  4986.5     .07       0
Bank Sta=4982.5,4986.5
XS Rating Curve= 0 ,0
Exp/Cntr=0.3,0.1

Type RM Length L Ch R = 1 ,28435   ,449,449,449
BEGIN DESCRIPTION:
Buffalo Creek 62.0
END DESCRIPTION:
XS GIS Cut Line= 3
      1847324.99       13895925.        1847475.       13895925.
      1847524.99       13895925.
#Sta/Elev= 28
  4849.6 2098.98  4852.1 2098.98  4859.6 2098.63  4869.6  2097.6  4879.6 2096.51
  4889.6 2095.61  4899.6 2093.99  4909.6 2092.58  4919.6 2091.33  4929.6  2089.5
  4939.6 2086.88  4949.6    2085  4959.6 2084.47  4969.6 2084.09  4977.6 2082.81
  4977.9 2082.31  4981.4 2082.31  4981.6 2082.81  4989.6 2083.48  4997.1 2084.52
  4999.6 2084.52  5002.1 2084.52  5009.6 2086.81  5019.6 2095.74  5029.6 2102.02
  5039.6 2105.25  5047.1 2106.65  5049.6 2106.65
#Mann= 3 ,-1 , 0
  4849.6     .07       0  4977.6     .05       0  4981.6     .07       0
Bank Sta=4977.6,4981.6
XS Rating Curve= 0 ,0
Exp/Cntr=0.3,0.1

Type RM Length L Ch R = 1 ,27986   ,469,469,469
BEGIN DESCRIPTION:
Buffalo Creek 61.0
END DESCRIPTION:
XS GIS Cut Line= 3
      1847224.99     13896174.99        1847375.       13896325.
      1847474.96     13896374.98
#Sta/Elev= 30
  4787.8 2096.57  4791.3 2096.57  4816.1 2095.17  4830.2 2093.31  4844.4 2090.85
  4866.7 2084.96  4872.7 2083.43  4886.8 2082.14  4915.1 2082.65  4929.2  2082.7
  4943.4 2082.31  4971.7 2080.29  4985.8 2079.02  4994.4 2077.17  4994.7 2076.67
  4998.2 2076.67  4998.4 2077.17  5002.7 2077.17  5008.3 2078.46  5013.9 2077.83
  5030.7 2078.43  5044.7 2084.72    5053 2088.88  5058.6 2095.11    5067 2100.17
    5081  2104.2  5089.4 2105.56  5097.8 2106.47  5108.9 2109.62  5111.7 2109.62
#Mann= 4 ,-1 , 0
  4787.8     .07       0  4866.7      .1       0  4994.4     .05       0
  4998.4      .1       0
Bank Sta=4994.4,4998.4
XS Rating Curve= 0 ,0
Exp/Cntr=0.3,0.1

Type RM Length L Ch R = 1 ,27517   ,422,422,422
BEGIN DESCRIPTION:
Buffalo Creek 60.0
END DESCRIPTION:
XS GIS Cut Line= 3
      1846975.01     13896425.02        1847025.       13896575.
      1847274.96     13896724.98
#Sta/Elev= 30
  4846.5  2091.4  4872.3 2089.36  4888.6 2088.25  4921.6 2084.22  4951.9 2074.07
    4971 2072.29  4971.2 2071.79  4974.7 2071.79    4975 2072.29  4994.1  2073.9
    5002 2075.94  5039.7  2074.9  5062.9 2075.84  5076.5 2078.36  5086.2 2080.97
  5097.9 2086.04  5113.4 2090.89  5121.2 2094.75    5129 2096.59  5156.2 2106.59
  5171.8 2107.74  5202.9 2114.62  5214.5 2117.78  5230.1 2120.03  5245.6 2123.69
  5261.2 2126.18  5282.5 2130.97  5288.4 2131.42  5293.2 2132.73  5296.1 2132.73
#Mann= 6 ,-1 , 0
  4846.5     .07       0  4872.3      .1       0  4921.6     .07       0
    4971     .05       0    4975     .07       0  5039.7      .1       0
Bank Sta=4971,4975
XS Rating Curve= 0 ,0
Exp/Cntr=0.3,0.1

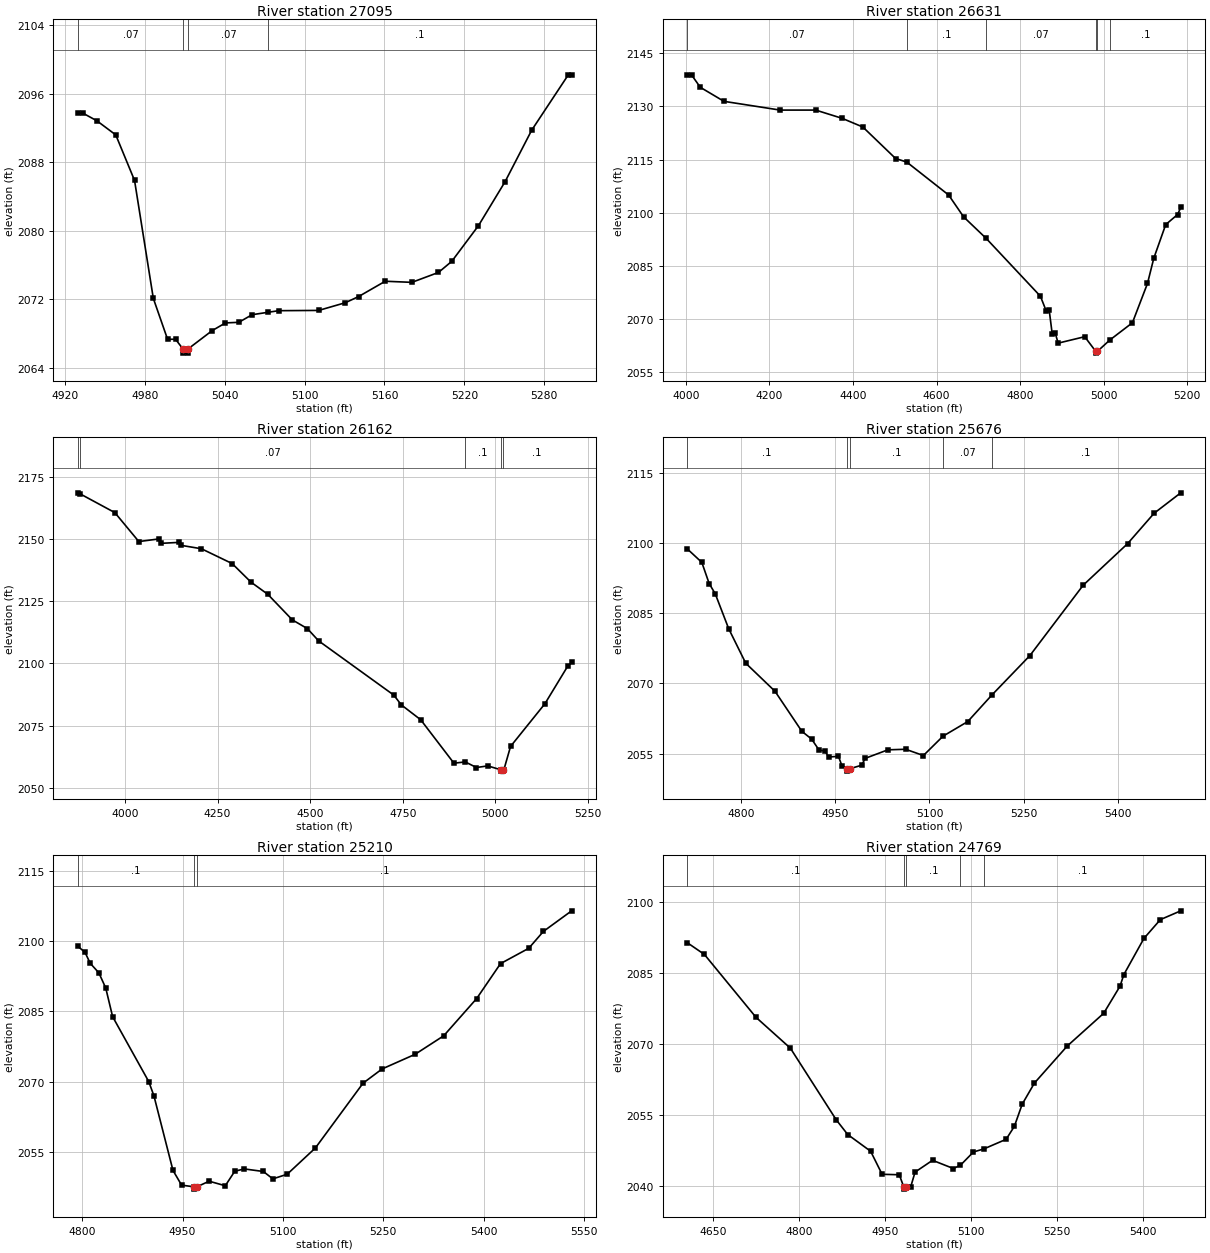
Type RM Length L Ch R = 1 ,27095   ,464,464,464
BEGIN DESCRIPTION:
Buffalo Creek 59.0
END DESCRIPTION:
XS GIS Cut Line= 3
      1846725.02     13896825.02        1846775.       13896875.
      1847075.01       13896875.
#Sta/Elev= 30
  4929.9 2093.75  4933.4 2093.75    4944 2092.85  4958.2  2091.2  4972.3 2085.88
  4986.4  2072.1  4997.1 2067.32  5003.1 2067.32  5008.6  2066.2  5008.8  2065.7
  5012.3  2065.7  5012.6  2066.2  5030.6 2068.33  5040.6 2069.23  5050.6  2069.3
  5060.6 2070.19  5072.9 2070.48  5080.6 2070.66  5110.6 2070.69  5130.6 2071.59
  5140.6 2072.31  5160.6  2074.1  5180.6 2073.97  5200.6 2075.13  5210.6 2076.43
  5230.6 2080.59  5250.6 2085.73  5270.6 2091.75  5298.1 2098.22  5300.6 2098.22
#Mann= 4 ,-1 , 0
  4929.9     .07       0  5008.6     .05       0  5012.6     .07       0
  5072.9      .1       0
Bank Sta=5008.6,5012.6
XS Rating Curve= 0 ,0
Exp/Cntr=0.3,0.1

Type RM Length L Ch R = 1 ,26631   ,469,469,469
BEGIN DESCRIPTION:
Buffalo Creek 58.0
END DESCRIPTION:
XS GIS Cut Line= 3
      1846083.62     13896651.92        1846825.       13897325.
      1846974.98     13897424.99
#Sta/Elev= 30
  4003.1 2138.77  4013.4 2138.93  4034.4 2135.41  4091.1 2131.44  4225.6 2128.97
  4310.8 2128.97  4374.3 2126.63  4423.7 2124.18    4502 2115.29  4528.7 2114.29
    4629 2104.98  4664.9  2098.8  4718.9 2092.72  4848.7 2076.39  4862.9 2072.15
  4869.6 2072.62  4877.1 2065.62  4883.8 2066.13  4891.2 2063.13  4954.8 2064.95
  4981.2 2060.81  4981.4 2060.31  4985.2 2060.81    5015 2064.02    5069 2068.89
  5105.1    2080  5120.1 2087.08  5148.7 2096.62  5177.2 2099.47  5184.7 2101.45
#Mann= 6 ,-1 , 0
  4003.1     .07       0  4528.7      .1       0  4718.9     .07       0
  4981.2     .05       0  4985.2     .07       0    5015      .1       0
Bank Sta=4981.2,4985.2
XS Rating Curve= 0 ,0
Exp/Cntr=0.3,0.1

Type RM Length L Ch R = 1 ,26162   ,486,486,486
BEGIN DESCRIPTION:
Buffalo Creek 57.0
END DESCRIPTION:
XS GIS Cut Line= 3
      1845665.08     13897967.44        1846775.       13897775.
      1846974.97     13897725.01
#Sta/Elev= 30
  3873.5 2168.49  3878.8 2168.09  3972.7 2160.55  4037.5 2148.93  4092.1 2149.99
  4097.2 2148.21  4146.8  2148.6  4151.9  2147.4  4206.5 2146.04  4289.5 2140.09
  4340.3 2132.64  4385.6 2127.77  4451.9 2117.49  4492.5 2113.99    4523 2109.06
    4726 2087.28  4746.2 2083.37  4798.6 2077.39  4888.3 2059.95  4918.8 2060.47
  4949.2 2058.22  4979.7 2058.87  5015.8 2057.27  5016.1 2056.77  5020.3 2057.27
  5023.2 2057.35  5041.2 2066.69    5134 2083.83  5195.8 2098.97  5206.1 2100.44
#Mann= 5 ,-1 , 0
  3873.5    .035       0  3878.8     .07       0  4918.8      .1       0
  5015.8     .05       0  5020.3      .1       0
Bank Sta=5015.8,5020.3
XS Rating Curve= 0 ,0
Exp/Cntr=0.3,0.1

Type RM Length L Ch R = 1 ,25676   ,466,466,466
BEGIN DESCRIPTION:
Buffalo Creek 56.0
END DESCRIPTION:
XS GIS Cut Line= 3
        1846625.       13898475.        1846775.       13898225.
      1847124.98     13897875.02
#Sta/Elev= 30
  4713.9 2098.76  4737.2 2095.86  4748.9 2091.34  4758.6 2089.15    4780  2081.7
  4807.2 2074.32  4853.8 2068.33  4896.6 2059.78  4912.2 2058.11  4923.8 2055.81
  4933.5 2055.54  4939.4 2054.29  4954.9 2054.43  4960.7 2052.34  4968.2 2051.77
  4968.5 2051.27  4972.7 2051.77  4991.8 2052.53  4997.7 2054.01  5033.7 2055.82
    5062 2055.94  5090.3  2054.6  5121.5 2058.73    5161 2061.86  5199.1 2067.48
    5260 2075.95  5344.9 2090.98  5415.6 2099.85    5458 2106.36  5500.4 2110.72
#Mann= 5 ,-1 , 0
  4713.9      .1       0  4968.2     .05       0  4972.7      .1       0
  5121.5     .07       0  5199.1      .1       0
Bank Sta=4968.2,4972.7
XS Rating Curve= 0 ,0
Exp/Cntr=0.3,0.1

Type RM Length L Ch R = 1 ,25210   ,441,441,441
BEGIN DESCRIPTION:
Buffalo Creek 55.0
END DESCRIPTION:
XS GIS Cut Line= 3
      1846774.96     13898675.01        1846975.       13898625.
      1847374.99       13898275.
#Sta/Elev= 30
  4793.8 2098.84  4804.2 2097.57  4811.9 2095.26  4824.8 2093.22  4835.1 2089.99
  4845.4 2083.87  4899.5    2070  4907.2 2066.96  4935.6 2051.09  4948.5 2047.94
  4966.8 2047.59  4967.1 2047.09  4971.4 2047.59  4989.7 2048.78  5013.8 2047.81
    5028 2050.91  5042.2  2051.4  5070.7 2050.85  5084.9 2049.28  5106.3 2050.26
  5148.5 2055.87  5219.7 2069.68  5248.2 2072.72  5297.5 2075.84  5340.3 2079.79
  5389.6 2087.74  5425.2 2095.18  5467.4 2098.45  5489.3 2102.05  5531.5 2106.44
#Mann= 3 ,-1 , 0
  4793.8      .1       0  4966.8     .05       0  4971.4      .1       0
Bank Sta=4966.8,4971.4
XS Rating Curve= 0 ,0
Exp/Cntr=0.3,0.1

Type RM Length L Ch R = 1 ,24769   ,419,419,419
BEGIN DESCRIPTION:
Buffalo Creek 54.0
END DESCRIPTION:
XS GIS Cut Line= 3
      1846824.95       13898975.        1847225.       13898975.
      1847524.99     13898625.02
#Sta/Elev= 30
  4604.7 2091.39  4634.7  2088.9  4724.7 2075.64  4784.7 2069.13  4864.7 2054.02
  4884.7 2050.92  4924.7 2047.39  4944.7 2042.53  4974.7 2042.43  4982.4  2039.9
  4982.7  2039.4    4987  2039.9  4994.7 2039.91  5002.2 2042.99  5032.7 2045.48
    5069 2043.75  5081.3 2044.43  5104.1 2047.24  5122.2 2047.88  5161.1 2049.91
  5175.4 2052.63  5189.1 2057.31  5210.5 2061.78  5267.6 2069.57  5331.3 2076.49
  5359.8 2082.21  5366.4 2084.64  5401.5 2092.28  5430.1 2096.24  5465.7  2098.1
#Mann= 5 ,-1 , 0
  4604.7      .1       0  4982.4     .05       0    4987      .1       0
  5081.3    .035       0  5122.2      .1       0
Bank Sta=4982.4,4987
XS Rating Curve= 0 ,0
Exp/Cntr=0.3,0.1

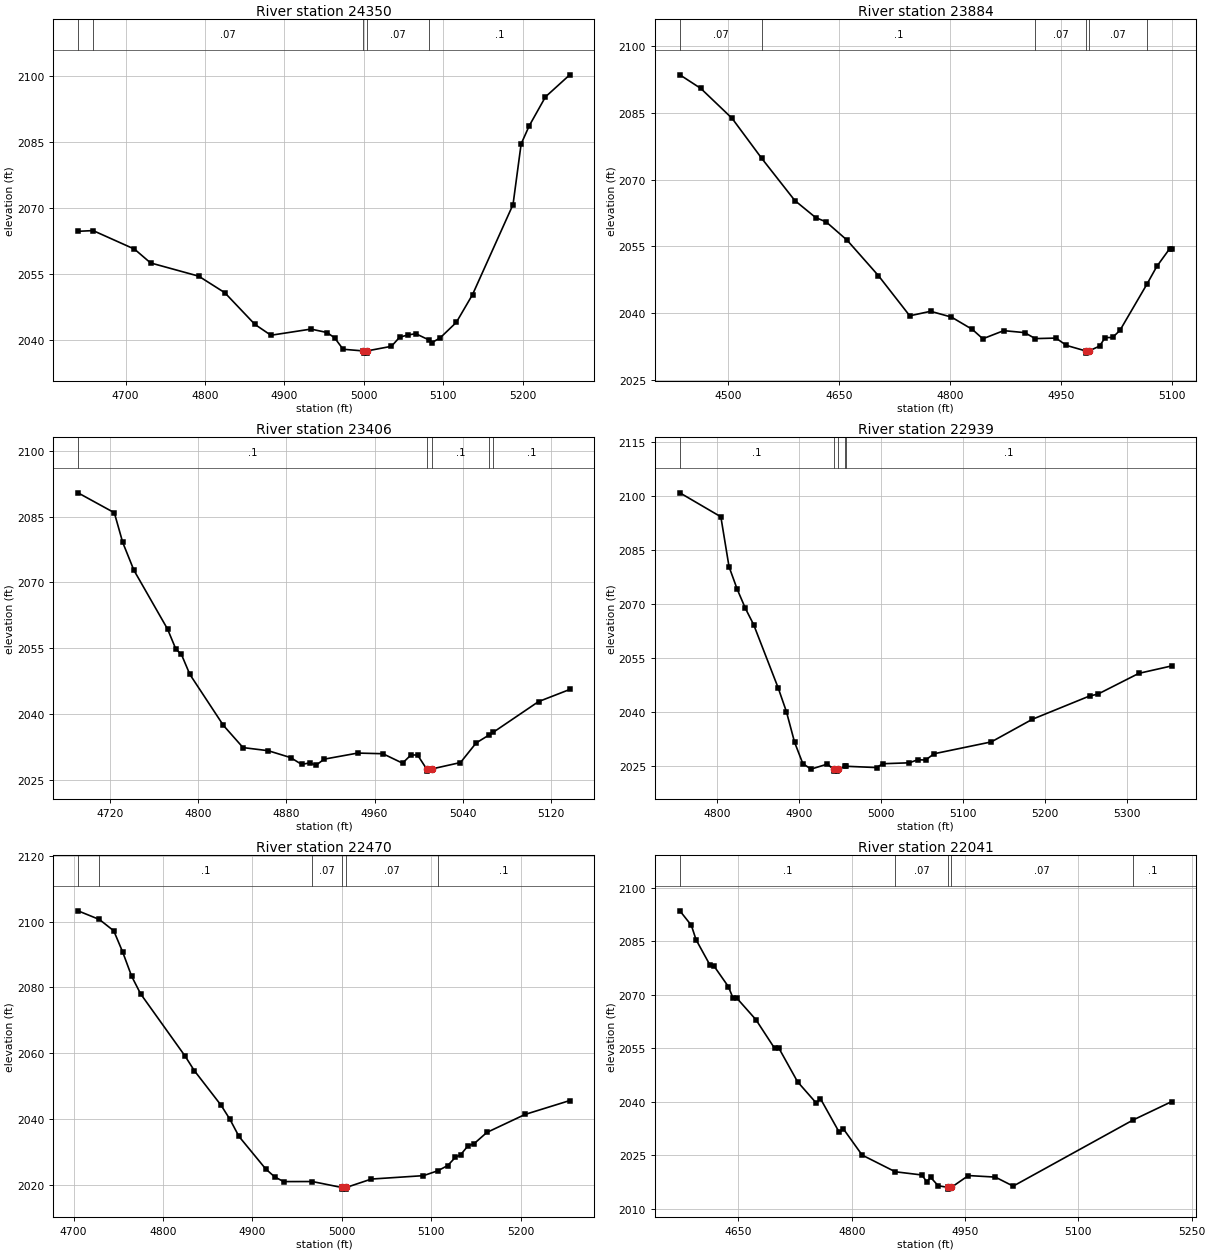
Type RM Length L Ch R = 1 ,24350   ,466,466,466
BEGIN DESCRIPTION:
Buffalo Creek 53.0
END DESCRIPTION:
XS GIS Cut Line= 3
      1847064.54     13899375.06        1847425.       13899325.
      1847675.03     13899375.01
#Sta/Elev= 30
  4640.2 2064.75  4659.2 2064.91  4711.3  2060.7  4731.5 2057.57  4792.1 2054.56
  4824.9 2050.81  4862.8 2043.61    4883 2041.14  4933.4 2042.54  4953.6 2041.76
  4963.2 2040.55  4973.8 2037.96  4999.2 2037.58  4999.6 2037.08  5003.6 2037.08
  5003.9 2037.58  5034.7 2038.63  5044.9 2040.68  5055.1  2041.2  5065.3 2041.49
  5081.8 2040.08  5085.7 2039.48  5095.9 2040.53  5116.3 2044.06  5136.7 2050.36
  5187.7 2070.83  5197.9  2084.6  5208.1 2088.71  5228.5 2095.28  5259.1 2100.29
#Mann= 5 ,-1 , 0
  4640.2    .035       0  4659.2     .07       0  4999.2     .05       0
  5003.9     .07       0  5081.8      .1       0
Bank Sta=4999.2,5003.9
XS Rating Curve= 0 ,0
Exp/Cntr=0.3,0.1

Type RM Length L Ch R = 1 ,23884   ,478,478,478
BEGIN DESCRIPTION:
Buffalo Creek 52.0
END DESCRIPTION:
XS GIS Cut Line= 3
      1847074.98     13900175.02        1847475.       13899775.
      1847574.99       13899775.
#Sta/Elev= 30
  4434.3 2093.61  4462.6 2090.55    4505 2083.81  4545.2 2074.78  4589.9 2065.31
  4618.2 2061.46  4632.3  2060.5  4660.6 2056.39    4703 2048.41  4745.5 2039.35
  4773.7 2040.37    4802 2039.06  4830.3 2036.28  4844.4 2034.18  4872.7 2036.01
    4901 2035.57  4915.4 2034.22  4943.4 2034.34  4957.6 2032.69  4983.5 2031.45
  4983.8 2030.95  4988.2 2031.45  5002.5 2032.54    5010 2034.45    5020 2034.47
    5030 2036.06  5066.4 2046.43    5080 2050.49  5097.5  2054.5    5100  2054.5
#Mann= 6 ,-1 , 0
  4434.3     .07       0  4545.2      .1       0  4915.4     .07       0
  4983.5     .05       0  4988.2     .07       0  5066.4      .1       0
Bank Sta=4983.5,4988.2
XS Rating Curve= 0 ,0
Exp/Cntr=0.3,0.1

Type RM Length L Ch R = 1 ,23406   ,467,467,467
BEGIN DESCRIPTION:
Buffalo Creek 51.0
END DESCRIPTION:
XS GIS Cut Line= 3
      1847525.01     13900524.95        1847575.       13900225.
      1847674.99     13900125.01
#Sta/Elev= 30
  4691.3 2090.42  4724.2 2085.88  4731.8 2079.11  4741.9 2072.78  4772.4 2059.35
    4780 2054.74    4785 2053.55  4792.6 2049.01    4823 2037.37  4840.8  2032.3
  4863.6 2031.59  4883.9 2030.02    4894 2028.45  4901.6 2028.84  4906.7 2028.23
  4914.3 2029.66  4944.7 2031.05  4967.5  2030.9  4985.3 2028.75  4992.9 2030.61
  4998.9 2030.61  5007.1 2027.43  5007.5 2026.93  5011.9 2027.43  5037.8 2028.89
    5052 2033.36  5063.6 2035.16  5067.3 2035.76  5108.5 2042.79  5136.8 2045.56
#Mann= 5 ,-1 , 0
  4691.3      .1       0  5007.1     .05       0  5011.9      .1       0
  5063.6     .07       0  5067.3      .1       0
Bank Sta=5007.1,5011.9
XS Rating Curve= 0 ,0
Exp/Cntr=0.3,0.1

Type RM Length L Ch R = 1 ,22939   ,469,469,469
BEGIN DESCRIPTION:
Buffalo Creek 50.0
END DESCRIPTION:
XS GIS Cut Line= 3
        1847975.     13900574.96        1847975.       13900325.
        1847975.     13899974.96
#Sta/Elev= 30
  4754.3 2100.86  4804.3 2094.21  4814.3 2080.35  4824.3 2074.08  4834.3 2068.77
  4844.3  2064.3  4874.3  2046.7  4884.3 2040.14  4894.3 2031.62  4904.3 2025.74
  4914.3 2024.19  4934.3  2025.6  4941.8 2024.14  4942.2 2023.64  4946.4 2023.64
  4946.7 2024.14  4956.1 2024.98  4956.7 2024.99  4994.3 2024.63  5001.8 2025.69
  5034.3 2025.95  5044.3 2026.78  5054.3 2026.73  5064.3 2028.45  5134.3 2031.75
  5184.3 2038.02  5254.3  2044.5  5264.3    2045  5314.3 2050.77  5354.3 2052.83
#Mann= 5 ,-1 , 0
  4754.3      .1       0  4941.8     .05       0  4946.7      .1       0
  4956.1     .07       0  4956.7      .1       0
Bank Sta=4941.8,4946.7
XS Rating Curve= 0 ,0
Exp/Cntr=0.3,0.1

Type RM Length L Ch R = 1 ,22470   ,429,429,429
BEGIN DESCRIPTION:
Buffalo Creek 49.0
END DESCRIPTION:
XS GIS Cut Line= 3
        1848375.     13900524.98        1848375.       13900225.
      1848224.99     13900024.98
#Sta/Elev= 30
    4705  2103.3  4728.9 2100.67    4745 2097.22    4755 2090.75    4765  2083.4
    4775 2078.07    4825 2059.04    4835 2054.74    4865 2044.19    4875 2039.87
    4885 2034.71    4915  2024.8    4925 2022.39    4935 2020.97  4967.1 2020.99
    5000 2019.18  5000.4 2018.68  5004.6 2018.68  5004.9 2019.18  5033.1 2021.74
  5091.4 2022.78  5107.4 2024.26  5118.5 2025.85  5126.9  2028.3  5133.1 2029.19
  5141.4 2031.91  5147.7 2032.43  5162.3 2035.92    5205 2041.39    5255 2045.61
#Mann= 6 ,-1 , 0
    4705     .07       0  4728.9      .1       0  4967.1     .07       0
    5000     .05       0  5004.9     .07       0  5107.4      .1       0
Bank Sta=5000,5004.9
XS Rating Curve= 0 ,0
Exp/Cntr=0.3,0.1

Type RM Length L Ch R = 1 ,22041   ,507,507,507
BEGIN DESCRIPTION:
Buffalo Creek 48.0
END DESCRIPTION:
XS GIS Cut Line= 3
      1848574.98     13900475.04        1848725.       13900075.
      1848624.98     13899874.96
#Sta/Elev= 30
  4572.5 2093.49  4587.7 2089.43  4593.9 2085.41  4612.6 2078.21  4617.9 2077.96
  4636.6  2072.3  4642.9 2069.05  4648.2 2068.97  4673.1 2063.03    4698 2054.96
  4703.4  2055.1  4728.3 2045.62  4753.2 2039.63  4758.6 2040.89  4783.5 2031.46
  4788.8 2032.48  4813.7 2025.11  4857.6 2020.43  4892.9 2019.53  4899.2 2017.63
  4904.5 2018.85  4914.3 2016.53  4926.9 2016.07  4927.3 2015.57  4931.9 2016.07
  4954.4 2019.37    4990 2018.94  5013.7 2016.41  5172.5 2034.94  5223.4 2040.07
#Mann= 5 ,-1 , 0
  4572.5      .1       0  4857.6     .07       0  4926.9     .05       0
  4931.9     .07       0  5172.5      .1       0
Bank Sta=4926.9,4931.9
XS Rating Curve= 0 ,0
Exp/Cntr=0.3,0.1