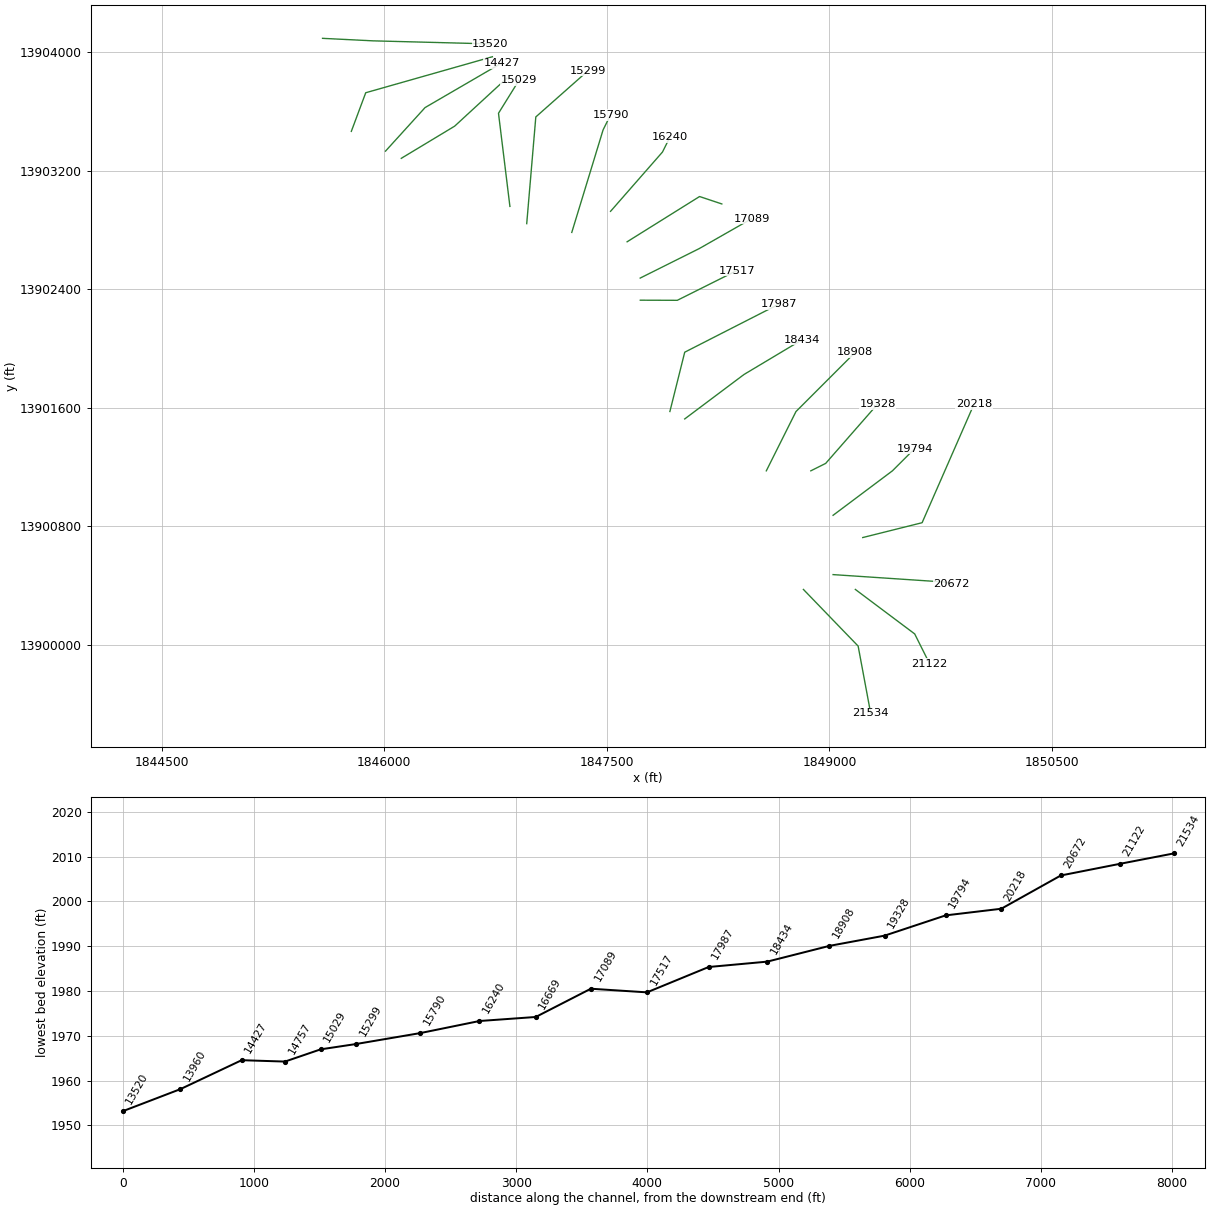
HEC-RAS study Buffalo Creek.prj: Buffalo Creek Base Level Engineering

--- Buffalo Creek.g01 (geometry) --- (continued)

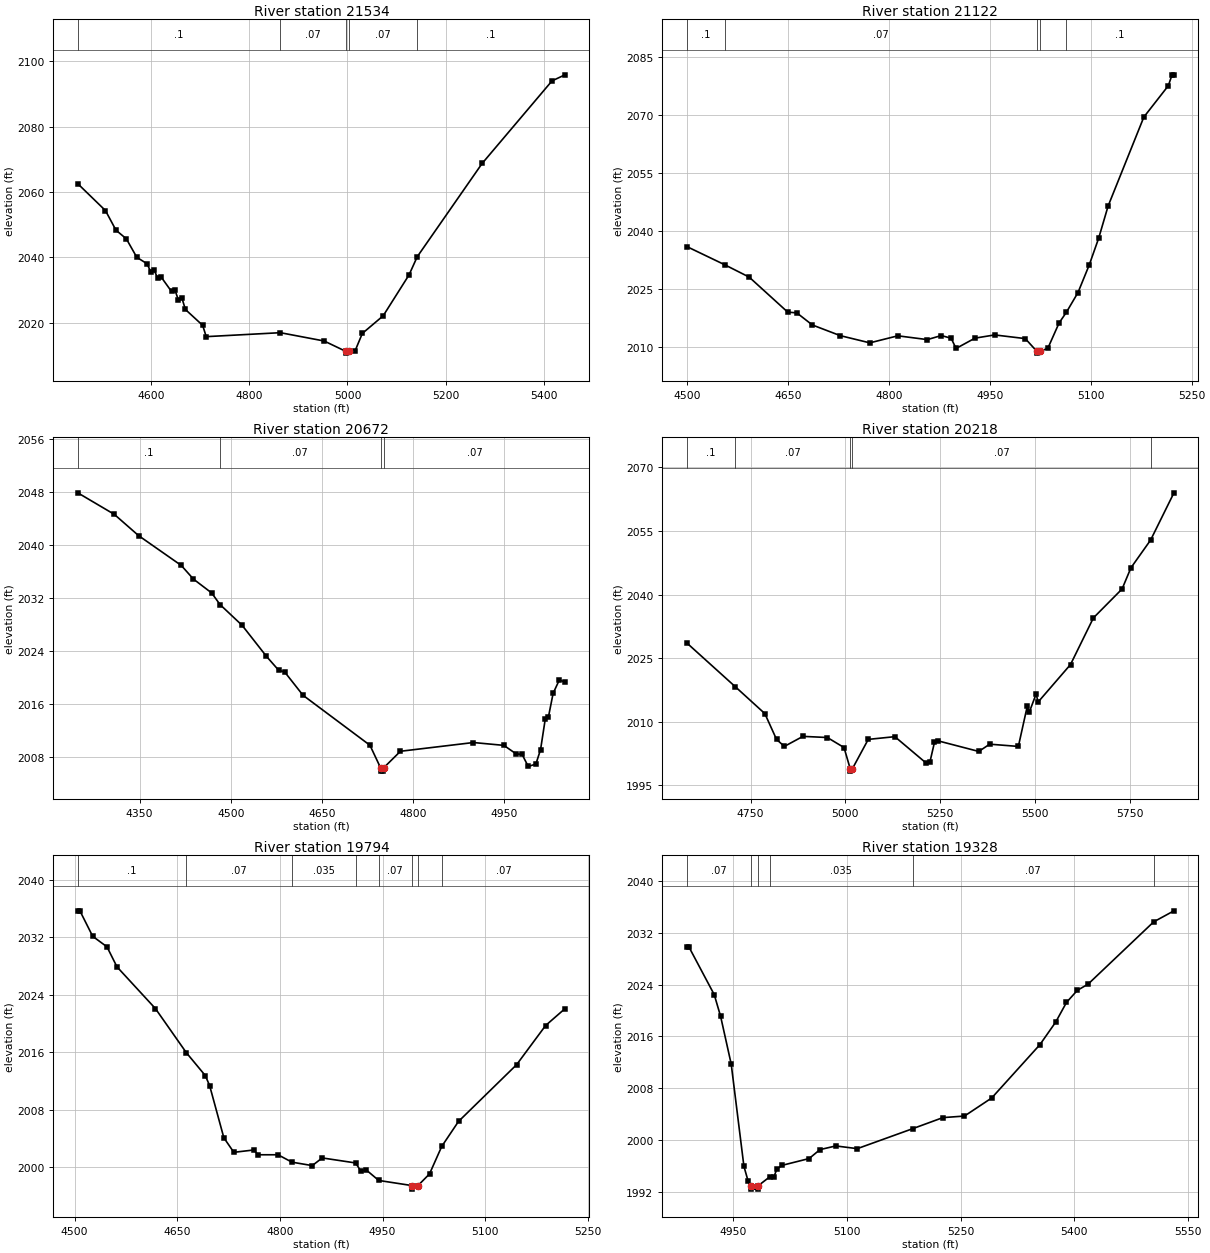
Type RM Length L Ch R = 1 ,21534   ,412,412,412
BEGIN DESCRIPTION:
Buffalo Creek 47.0
END DESCRIPTION:
XS GIS Cut Line= 3
      1848825.03     13900374.97      1849193.91     13899992.79
      1849278.42     13899539.05
#Sta/Elev= 30
  4450.5 2062.55  4506.9 2054.34  4528.3 2048.34  4549.4 2045.71  4570.7 2040.06
  4591.8 2038.05    4599 2035.62    4606 2036.23  4613.2 2033.63  4620.1 2034.07
  4641.5 2029.59  4648.4 2030.03  4655.6    2027  4662.6 2027.61  4669.8 2024.09
    4705 2019.23  4712.2 2015.78  4863.2 2016.99  4952.5 2014.45  4997.2 2011.24
  4997.6 2010.74  5002.3 2011.24    5015 2011.24  5030.3 2016.77  5072.8 2022.16
  5125.5 2034.67  5142.1  2040.2  5274.4 2068.75  5416.8    2094  5443.2 2095.85
#Mann= 5 ,-1 , 0
  4450.5      .1       0  4863.2     .07       0  4997.2     .05       0
  5002.3     .07       0  5142.1      .1       0
Bank Sta=4997.2,5002.3
XS Rating Curve= 0 ,0
Exp/Cntr=0.3,0.1

Type RM Length L Ch R = 1 ,21122   ,450,450,450
BEGIN DESCRIPTION:
Buffalo Creek 46.0
END DESCRIPTION:
XS GIS Cut Line= 3
        1849175.       13900375.        1849575.       13900075.
        1849675.       13899875.
#Sta/Elev= 30
    4500    2036  4556.3 2031.29  4592.7 2028.09    4650 2019.02  4663.5 2018.83
  4686.5  2015.7  4728.1 2012.93  4771.9 2011.07  4813.5 2012.89  4857.3 2011.91
  4878.1 2012.96  4892.7 2012.26    4900 2009.62  4928.1 2012.29  4957.3 2013.12
  5002.8 2012.17  5019.8 2008.91  5020.2 2008.41  5024.9 2008.91  5036.3 2009.66
  5053.1 2016.25  5063.7 2018.94  5081.1 2024.09  5097.8 2031.24  5111.8 2038.15
  5125.8 2046.47  5178.9 2069.51  5215.2 2077.61  5220.8 2080.44  5223.6 2080.44
#Mann= 5 ,-1 , 0
    4500      .1       0  4556.3     .07       0  5019.8     .05       0
  5024.9     .07       0  5063.7      .1       0
Bank Sta=5019.8,5024.9
XS Rating Curve= 0 ,0
Exp/Cntr=0.3,0.1

Type RM Length L Ch R = 1 ,20672   ,454,454,454
BEGIN DESCRIPTION:
Buffalo Creek 45.0
END DESCRIPTION:
XS GIS Cut Line= 3
      1849025.02       13900475.        1849775.       13900425.
      1849823.96     13900412.79
#Sta/Elev= 30
  4248.2 2047.85  4308.3  2044.6  4348.4 2041.38  4418.6 2036.88  4438.6 2034.82
  4468.7 2032.72  4482.3 2030.98  4518.8 2027.83  4558.9 2023.14  4578.9 2021.05
  4588.9 2020.78    4619 2017.27  4729.2 2009.72  4746.7 2006.31  4747.1 2005.81
  4751.4 2005.81  4751.8 2006.31  4779.4 2008.81  4899.6 2010.13  4949.7  2009.7
  4969.8 2008.42  4979.8 2008.33  4989.8 2006.51  5002.4 2006.88  5010.1 2009.06
  5017.9 2013.71  5023.1 2014.01  5030.8 2017.57  5041.1  2019.6  5050.3 2019.23
#Mann= 4 ,-1 , 0
  4248.2      .1       0  4482.3     .07       0  4746.7     .05       0
  4751.8     .07       0
Bank Sta=4746.7,4751.8
XS Rating Curve= 0 ,0
Exp/Cntr=0.3,0.1

Type RM Length L Ch R = 1 ,20218   ,424,424,424
BEGIN DESCRIPTION:
Buffalo Creek 44.0
END DESCRIPTION:
XS GIS Cut Line= 3
      1849225.04     13900725.01        1849625.       13900825.
      1849975.01     13901625.01
#Sta/Elev= 30
  4581.6  2028.6  4710.2 2018.23  4787.7 2011.93  4818.6 2005.84  4839.3 2004.21
  4888.2 2006.57  4952.6  2006.3  4996.6 2003.94  5013.1 1998.88  5013.5 1998.38
  5018.3 1998.88  5060.5 2005.86  5130.7  2006.5  5212.2 2000.36  5223.1 2000.47
  5235.2 2005.16  5244.9 2005.51  5352.1 2003.02    5381 2004.73  5456.6  2004.2
    5480 2013.63  5485.4 2012.27  5503.4 2016.55  5508.8 2014.67  5594.2  2023.5
  5654.6 2034.49  5730.3 2041.31  5753.6 2046.29  5805.6 2052.84  5867.1 2063.96
#Mann= 5 ,-1 , 0
  4581.6      .1       0  4710.2     .07       0  5013.1     .05       0
  5018.3     .07       0  5805.6      .1       0
Bank Sta=5013.1,5018.3
XS Rating Curve= 0 ,0
Exp/Cntr=0.3,0.1

Type RM Length L Ch R = 1 ,19794   ,466,466,466
BEGIN DESCRIPTION:
Buffalo Creek 43.0
END DESCRIPTION:
XS GIS Cut Line= 3
      1849025.02     13900875.02        1849425.       13901175.
        1849575.       13901325.
#Sta/Elev= 30
  4504.6  2035.7  4507.7  2035.7  4526.4 2032.15  4547.3 2030.68  4561.9 2027.89
  4618.1 2022.07  4663.3 2015.92    4691 2012.73  4697.3 2011.34  4718.1 2004.06
  4732.7 2002.03  4761.9 2002.36  4768.1 2001.69  4797.3 2001.69  4817.6 2000.66
  4847.3 2000.18  4861.9 2001.25  4910.7 2000.55  4918.1 1999.45  4926.4 1999.56
  4944.5 1998.11  4992.7  1997.4  4993.2  1996.9  5001.9  1997.4  5018.7 1999.02
  5036.6 2002.86  5061.1 2006.34    5146 2014.25  5188.4 2019.71  5216.7 2022.06
#Mann= 8 ,-1 , 0
  4504.6      .1       0  4663.3     .07       0  4817.6    .035       0
  4910.7     .07       0  4944.5     .07       0  4992.7     .05       0
  5001.9     .07       0  5036.6     .07       0
Bank Sta=4992.7,5001.9
XS Rating Curve= 0 ,0
Exp/Cntr=0.3,0.1

Type RM Length L Ch R = 1 ,19328   ,420,420,420
BEGIN DESCRIPTION:
Buffalo Creek 42.0
END DESCRIPTION:
XS GIS Cut Line= 3
      1848874.99       13901175.        1848975.       13901225.
      1849324.99     13901624.98
#Sta/Elev= 30
  4888.5 2029.84  4891.3 2029.84  4924.8 2022.45  4933.2  2019.1  4947.2 2011.72
    4964 1995.89  4969.6 1993.59  4973.3 1992.87  4973.8 1992.37  4982.1 1992.37
  4982.6 1992.87  4998.4  1994.3  5003.6  1994.3  5007.4 1995.42  5014.1 1996.04
  5050.1  1997.1  5064.4 1998.48  5085.3 1999.05  5113.7 1998.63  5187.1 2001.73
  5226.7 2003.43  5255.2 2003.67  5291.2 2006.47  5354.8 2014.71  5375.7 2018.21
  5389.9 2021.24  5404.2 2023.11  5418.4 2024.07    5505  2033.7  5531.8 2035.41
#Mann= 6 ,-1 , 0
  4888.5     .07       0  4973.3     .05       0  4982.6     .07       0
  4998.4    .035       0  5187.1     .07       0    5505      .1       0
Bank Sta=4973.3,4982.6
XS Rating Curve= 0 ,0
Exp/Cntr=0.3,0.1

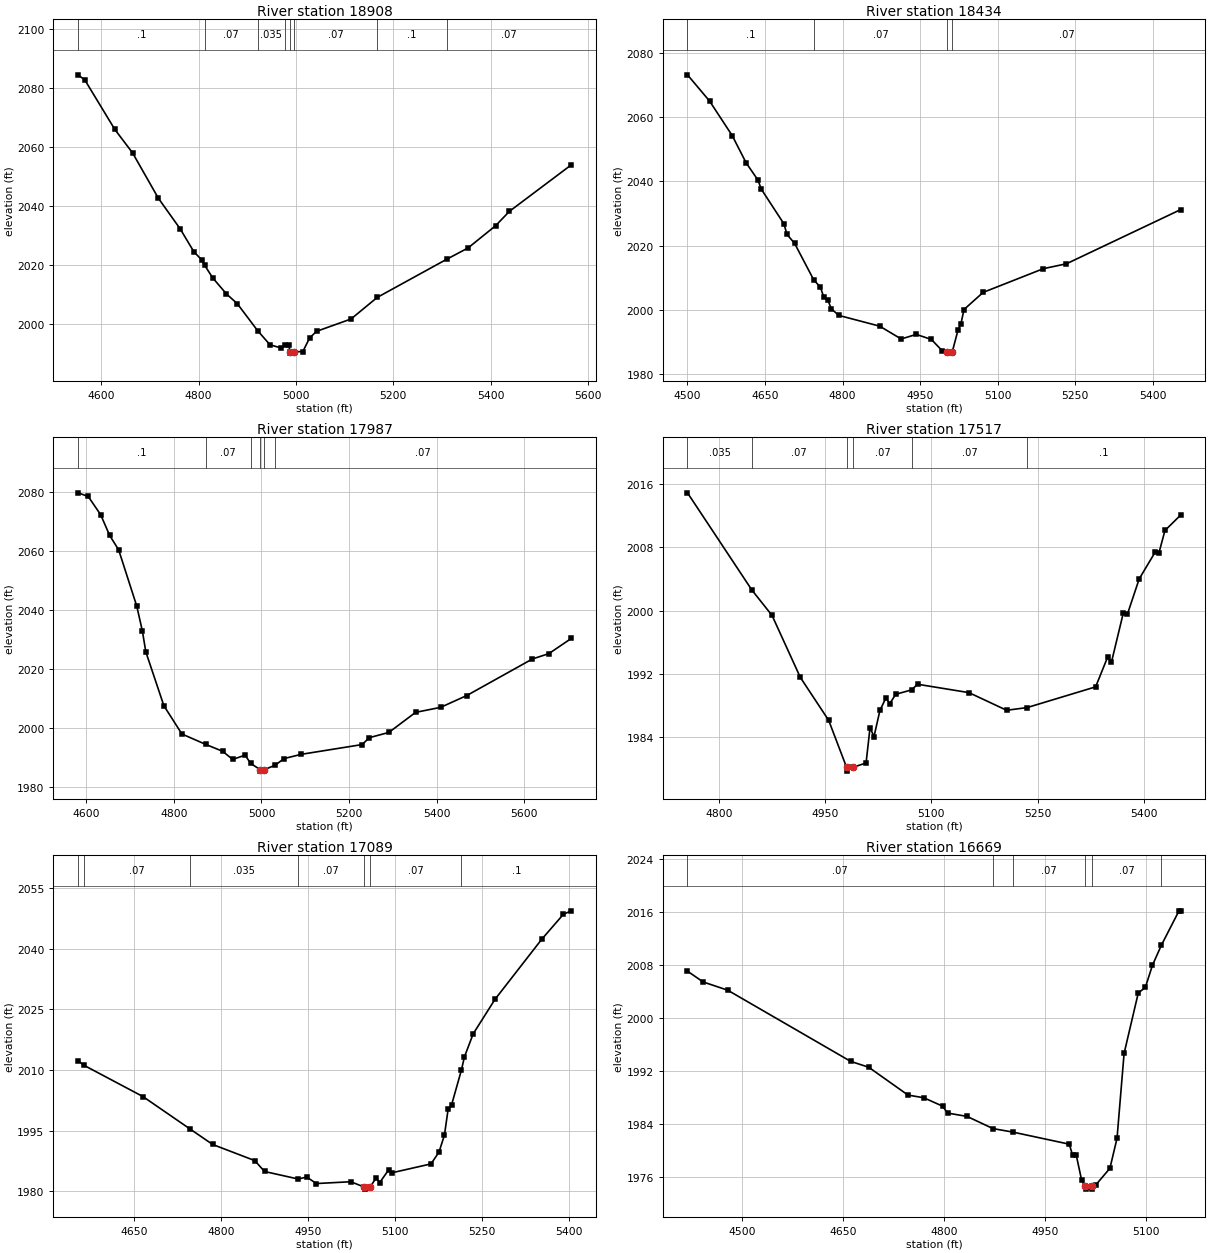
Type RM Length L Ch R = 1 ,18908   ,474,474,474
BEGIN DESCRIPTION:
Buffalo Creek 41.0
END DESCRIPTION:
XS GIS Cut Line= 3
      1848574.99     13901174.99        1848775.       13901575.
      1849174.99     13901974.99
#Sta/Elev= 30
  4552.7 2084.55  4566.7 2082.77  4628.2    2066  4664.5 2058.08  4717.6 2042.65
  4762.3 2032.28  4790.3 2024.55  4807.1 2021.63  4812.5 2019.92  4829.4 2015.58
  4857.4 2010.18  4879.7 2006.86  4921.4 1997.71  4946.8 1992.92  4969.2 1991.85
  4977.8 1992.69    4986    1993  4986.9 1990.59  4987.4 1990.09  4996.2 1990.59
  5014.1  1990.6  5028.2 1995.25  5042.4 1997.49  5113.1 2001.67    5167    2009
  5310.7 2022.05  5353.5 2025.79  5410.1 2033.34  5438.3  2038.2  5565.6 2054.01
#Mann= 8 ,-1 , 0
  4552.7      .1       0  4812.5     .07       0  4921.4    .035       0
  4977.8     .07       0  4986.9     .05       0  4996.2     .07       0
    5167      .1       0  5310.7     .07       0
Bank Sta=4986.9,4996.2
XS Rating Curve= 0 ,0
Exp/Cntr=0.3,0.1

Type RM Length L Ch R = 1 ,18434   ,447,447,447
BEGIN DESCRIPTION:
Buffalo Creek 40.0
END DESCRIPTION:
XS GIS Cut Line= 3
        1848025.       13901525.        1848425.       13901825.
      1848814.91     13902058.35
#Sta/Elev= 30
    4500 2073.16  4542.7 2065.01  4586.5 2054.27  4613.5 2045.78  4636.5 2040.38
  4642.7 2037.62  4686.5 2026.82  4692.7 2023.48  4707.3 2020.71  4744.1 2009.42
  4757.3 2007.05  4763.5 2004.09  4771.9 2002.97  4778.1  2000.4  4792.7 1998.31
  4871.9 1994.96  4913.5 1990.97  4942.7  1992.4  4971.9 1990.82  4992.7 1987.34
  5003.1 1987.07  5003.6 1986.57  5012.5 1987.07  5023.3 1993.68  5029.2 1995.76
    5035 2000.14    5072 2005.46  5188.6 2012.85  5233.1 2014.36  5454.4 2031.24
#Mann= 4 ,-1 , 0
    4500      .1       0  4744.1     .07       0  5003.1     .05       0
  5012.5     .07       0
Bank Sta=5003.1,5012.5
XS Rating Curve= 0 ,0
Exp/Cntr=0.3,0.1

Type RM Length L Ch R = 1 ,17987   ,470,470,470
BEGIN DESCRIPTION:
Buffalo Creek 39.0
END DESCRIPTION:
XS GIS Cut Line= 3
      1847925.01     13901575.04        1848025.       13901975.
      1848660.72     13902299.66
#Sta/Elev= 30
  4581.4 2079.58  4604.6 2078.34  4632.9 2072.18  4653.5 2065.16  4674.1 2060.25
  4715.4 2041.21  4728.2 2032.79    4736 2025.77  4777.2 2007.53  4818.4 1997.94
  4873.2 1994.39  4911.2  1992.1  4934.4 1989.33  4962.7 1990.78  4975.5 1987.96
  4997.2 1985.87  4997.7 1985.37  5006.7 1985.87  5031.1 1987.37    5052 1989.63
  5090.9 1991.06  5229.8 1994.36  5246.4  1996.7  5290.9 1998.47  5351.9 2005.26
  5409.1 2006.96  5468.6 2010.95  5618.6 2023.34  5656.2 2025.15  5707.5 2030.31
#Mann= 6 ,-1 , 0
  4581.4      .1       0  4873.2     .07       0  4975.5     .07       0
  4997.2     .05       0  5006.7     .07       0  5031.1     .07       0
Bank Sta=4997.2,5006.7
XS Rating Curve= 0 ,0
Exp/Cntr=0.3,0.1

Type RM Length L Ch R = 1 ,17517   ,428,428,428
BEGIN DESCRIPTION:
Buffalo Creek 38.0
END DESCRIPTION:
XS GIS Cut Line= 3
      1847725.59     13902325.83        1847975.       13902325.
      1848374.98     13902524.99
#Sta/Elev= 30
  4755.6 2014.88  4846.6 2002.59    4875 1999.39    4915 1991.55    4955 1986.13
  4980.2 1980.21  4980.7 1979.71  4989.8 1980.21  5007.8 1980.74  5013.4 1985.19
    5019 1984.08  5027.4 1987.38  5035.8 1988.96  5041.3 1988.24  5049.7 1989.42
  5072.2 1989.98  5080.5 1990.69  5153.1 1989.63  5206.3  1987.4  5235.2 1987.74
    5332 1990.36  5348.8 1994.09  5354.4  1993.5  5371.2 1999.74  5376.8 1999.52
  5393.5    2004  5415.9 2007.36  5421.5 2007.32  5429.9 2010.12  5452.2 2012.08
#Mann= 6 ,-1 , 0
  4755.6    .035       0  4846.6     .07       0  4980.2     .05       0
  4989.8     .07       0  5072.2     .07       0  5235.2      .1       0
Bank Sta=4980.2,4989.8
XS Rating Curve= 0 ,0
Exp/Cntr=0.3,0.1

Type RM Length L Ch R = 1 ,17089   ,420,420,420
BEGIN DESCRIPTION:
Buffalo Creek 37.0
END DESCRIPTION:
XS GIS Cut Line= 3
      1847725.03     13902475.02        1848125.       13902675.
      1848475.01       13902875.
#Sta/Elev= 30
  4553.5 2012.28    4563 2011.19  4665.3 2003.41    4746 1995.44  4785.5 1991.56
  4858.1 1987.57  4874.9 1984.88    4933 1983.02  4947.6 1983.51  4964.3  1981.9
  5023.7 1982.35  5046.9 1981.02  5047.4 1980.52  5056.6 1981.02  5067.6 1983.33
  5073.4 1982.13  5089.2 1985.36    5095 1984.58  5161.9 1986.76  5175.6 1989.68
    5185 1993.86  5191.4  2000.3  5197.2 2001.29  5214.3 2009.98  5219.5 2013.24
  5234.6 2018.93  5272.1 2027.44  5352.7  2042.3  5390.1 2048.49  5403.8 2049.34
#Mann= 7 ,-1 , 0
  4553.5    .035       0    4563     .07       0    4746    .035       0
    4933     .07       0  5046.9     .05       0  5056.6     .07       0
  5214.3      .1       0
Bank Sta=5046.9,5056.6
XS Rating Curve= 0 ,0
Exp/Cntr=0.3,0.1

Type RM Length L Ch R = 1 ,16669   ,429,429,429
BEGIN DESCRIPTION:
Buffalo Creek 36.0
END DESCRIPTION:
XS GIS Cut Line= 3
      1847636.85     13902719.79        1848125.       13903025.
      1848274.97     13902975.01
#Sta/Elev= 30
  4418.4 2007.09  4441.7 2005.46  4478.2 2004.22    4661 1993.49  4688.1 1992.59
  4746.4  1988.4    4770 1987.99  4797.8 1986.73  4805.4 1985.68  4834.3 1985.18
  4872.9 1983.34  4902.1 1982.82  4986.4 1980.99  4991.2 1979.36  4996.7 1979.36
  5004.7 1975.58  5010.3 1974.71  5010.8 1974.21  5019.5 1974.21    5020 1974.71
  5025.7 1974.83  5046.8 1977.35  5057.4 1981.87  5067.9 1994.67    5089  2003.8
  5099.5 2004.63  5110.1 2007.98  5123.4 2011.01  5149.6 2016.19  5152.2 2016.19
#Mann= 6 ,-1 , 0
  4418.4     .07       0  4872.9    .035       0  4902.1     .07       0
  5010.3     .05       0    5020     .07       0  5123.4      .1       0
Bank Sta=5010.3,5020
XS Rating Curve= 0 ,0
Exp/Cntr=0.3,0.1

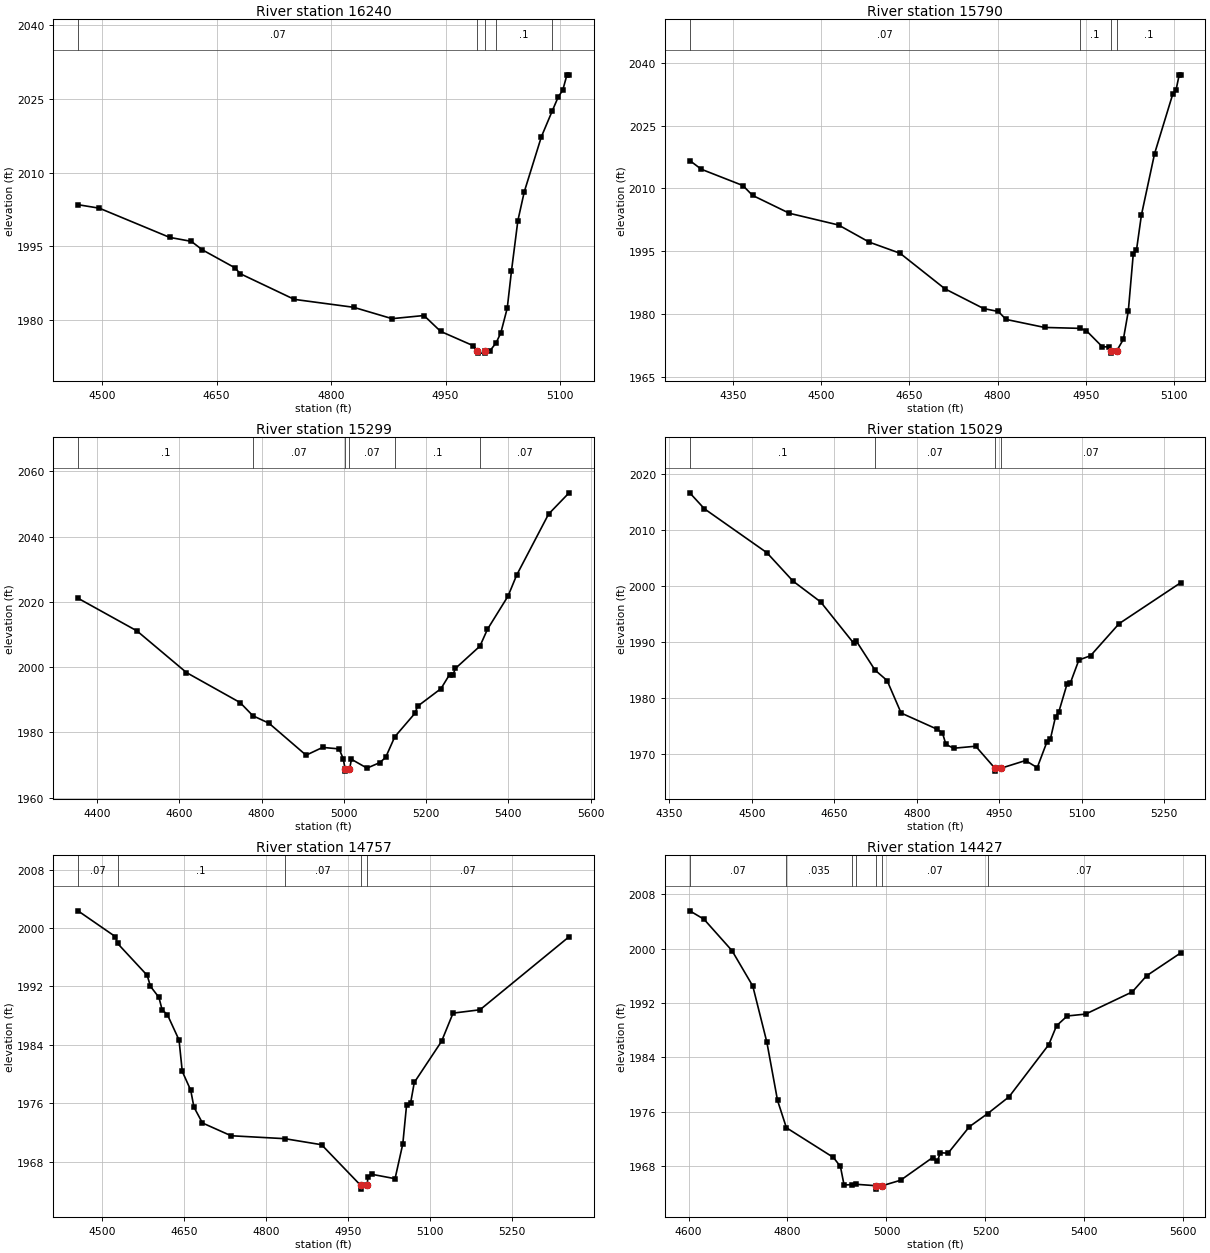
Type RM Length L Ch R = 1 ,16240   ,450,450,450
BEGIN DESCRIPTION:
Buffalo Creek 35.0
END DESCRIPTION:
XS GIS Cut Line= 3
        1847525.       13902925.        1847875.       13903325.
      1847924.99     13903424.99
#Sta/Elev= 30
  4468.5 2003.46  4496.5 2002.75  4588.6 1996.82    4617 1996.01  4631.3  1994.3
    4674 1990.65  4681.1 1989.44  4751.8 1984.23  4829.6 1982.62  4879.9 1980.31
  4921.7 1980.95  4943.5 1977.73  4986.2 1974.82  4991.5 1973.81    4992 1973.31
  5001.3 1973.31  5001.8 1973.81  5008.4 1973.83  5016.2 1975.39  5022.4 1977.44
  5030.8 1982.45  5036.3 1989.95  5044.7 2000.22  5053.1 2006.08  5075.5 2017.26
  5089.5 2022.42  5097.8 2025.43  5103.4 2026.67    5109 2029.84  5111.8 2029.84
#Mann= 5 ,-1 , 0
  4468.5     .07       0  4991.5     .05       0  5001.8     .07       0
  5016.2      .1       0  5089.5     .07       0
Bank Sta=4991.5,5001.8
XS Rating Curve= 0 ,0
Exp/Cntr=0.3,0.1

Type RM Length L Ch R = 1 ,15790   ,491,491,491
BEGIN DESCRIPTION:
Buffalo Creek 34.0
END DESCRIPTION:
XS GIS Cut Line= 3
       1847263.8      13902782.9        1847475.       13903475.
      1847524.99     13903574.99
#Sta/Elev= 30
  4276.3 2016.65  4295.9 2014.57  4366.7 2010.67  4383.1 2008.32  4445.8 2004.04
  4529.4 2001.24  4581.7 1997.14    4634 1994.49  4710.5 1985.98  4776.2 1981.27
  4801.3 1980.57  4814.2 1978.68  4879.8 1976.76  4939.7 1976.54  4950.7 1976.02
  4978.3 1972.11  4989.5 1972.13  4992.1 1971.12  4992.6 1970.62  5002.4 1971.12
  5013.9 1973.91  5022.3 1980.66  5030.7 1994.24  5036.2 1995.24  5044.6 2003.62
    5067  2018.3  5097.7 2032.43  5103.3  2033.4  5108.9 2037.13  5111.7 2037.13
#Mann= 4 ,-1 , 0
  4276.3     .07       0  4939.7      .1       0  4992.1     .05       0
  5002.4      .1       0
Bank Sta=4992.1,5002.4
XS Rating Curve= 0 ,0
Exp/Cntr=0.3,0.1

Type RM Length L Ch R = 1 ,15299   ,270,270,270
BEGIN DESCRIPTION:
Buffalo Creek 33.0
END DESCRIPTION:
XS GIS Cut Line= 3
       1846960.1     13902842.08      1847021.41     13903561.86
        1847375.       13903875.
#Sta/Elev= 30
  4353.2 2021.11  4496.6 2011.11  4617.1 1998.35  4747.5 1989.17  4778.8 1985.12
  4817.8 1982.84  4908.1 1973.05  4948.3 1975.43  4988.4 1974.98  4998.4 1971.99
  5003.3 1968.67  5003.8 1968.17  5013.6 1968.67  5018.5 1971.79  5056.3 1969.09
  5087.5 1970.78  5101.7 1972.39  5123.9 1978.69  5172.8 1985.86  5179.5 1988.04
  5236.3 1993.43  5257.2 1997.75  5264.8 1997.52  5271.5 1999.63  5331.1 2006.45
  5349.2 2011.57  5399.4 2021.76  5420.3 2028.17  5498.1 2046.89  5547.9 2053.38
#Mann= 6 ,-1 , 0
  4353.2      .1       0  4778.8     .07       0  5003.3     .05       0
  5013.6     .07       0  5123.9      .1       0  5331.1     .07       0
Bank Sta=5003.3,5013.6
XS Rating Curve= 0 ,0
Exp/Cntr=0.3,0.1

Type RM Length L Ch R = 1 ,15029   ,272,272,272
BEGIN DESCRIPTION:
Buffalo Creek 32.0
END DESCRIPTION:
XS GIS Cut Line= 3
       1846846.8     13902958.46      1846769.89     13903586.58
      1846907.47     13903808.37
#Sta/Elev= 30
  4386.9 2016.61  4413.6 2013.76  4527.3 2005.93  4574.8 2000.87  4625.2 1997.15
  4685.2  1989.8  4690.2 1990.15    4724 1985.01  4746.1 1983.13  4771.6 1977.34
  4836.8 1974.47  4846.8 1973.79  4853.1 1971.76    4867 1971.06  4907.3 1971.42
  4942.4 1967.48  4942.9 1966.98  4952.8 1967.48    4998 1968.87  5019.3  1967.6
  5037.2 1972.25  5043.1 1972.65  5052.6 1976.68  5058.4 1977.49  5073.8 1982.59
  5079.7 1982.73  5095.1  1986.8  5116.3 1987.56  5168.3 1993.28  5280.7  2000.6
#Mann= 4 ,-1 , 0
  4386.9      .1       0    4724     .07       0  4942.4     .05       0
  4952.8     .07       0
Bank Sta=4942.4,4952.8
XS Rating Curve= 0 ,0
Exp/Cntr=0.3,0.1

Type RM Length L Ch R = 1 ,14757   ,330,330,330
BEGIN DESCRIPTION:
Buffalo Creek 31.1
END DESCRIPTION:
XS GIS Cut Line= 3
      1846114.69     13903282.64      1846474.23     13903499.49
      1846826.26     13903823.78
#Sta/Elev= 30
  4455.5 2002.36    4524 1998.82  4527.9  1997.9  4582.2 1993.52    4588 1992.03
  4603.6 1990.51  4609.4 1988.82  4619.1 1988.14  4640.4 1984.67  4646.3 1980.37
  4661.8 1977.79  4667.6 1975.49  4683.2 1973.31  4735.6 1971.56  4833.7 1971.16
  4901.2 1970.33  4972.9 1964.75  4973.4 1964.25  4984.9 1964.75  4985.7  1965.9
  4993.1 1966.28  5035.6 1965.68  5049.8 1970.45  5056.6 1975.71    5064 1976.02
  5070.8 1978.86  5120.7 1984.49  5141.7 1988.35    5191 1988.81    5354 1998.81
#Mann= 5 ,-1 , 0
  4455.5     .07       0  4527.9      .1       0  4833.7     .07       0
  4972.9     .05       0  4984.9     .07       0
Bank Sta=4972.9,4984.9
XS Rating Curve= 0 ,0
Exp/Cntr=0.3,0.1

Type RM Length L Ch R = 1 ,14427   ,467,467,467
BEGIN DESCRIPTION:
Buffalo Creek 31.0
END DESCRIPTION:
XS GIS Cut Line= 3
      1846008.33     13903331.26        1846275.       13903625.
      1846789.85     13903924.78
#Sta/Elev= 30
  4602.5 2005.58  4631.3 2004.34    4688  1999.7  4729.9 1994.49  4758.3 1986.23
  4779.9 1977.64  4797.8 1973.61  4892.8 1969.23    4907  1967.9  4914.4 1965.16
  4930.5 1965.23  4939.4 1965.27  4979.4 1965.06  4979.9 1964.56  4991.4 1965.06
  5028.6 1965.87  5093.1  1969.2  5103.1 1968.72  5108.9 1969.92  5124.6 1969.86
  5167.6 1973.76  5204.7  1975.7  5247.8 1978.17  5328.1 1985.86  5343.8 1988.64
  5365.3 1990.08  5402.5 1990.36  5496.8 1993.63  5525.8 1996.01    5595 1999.39
#Mann= 7 ,-1 , 0
  4602.5     .07       0  4797.8    .035       0  4930.5     .07       0
  4939.4     .07       0  4979.4     .05       0  4991.4     .07       0
  5204.7     .07       0
Bank Sta=4979.4,4991.4
XS Rating Curve= 0 ,0
Exp/Cntr=0.3,0.1

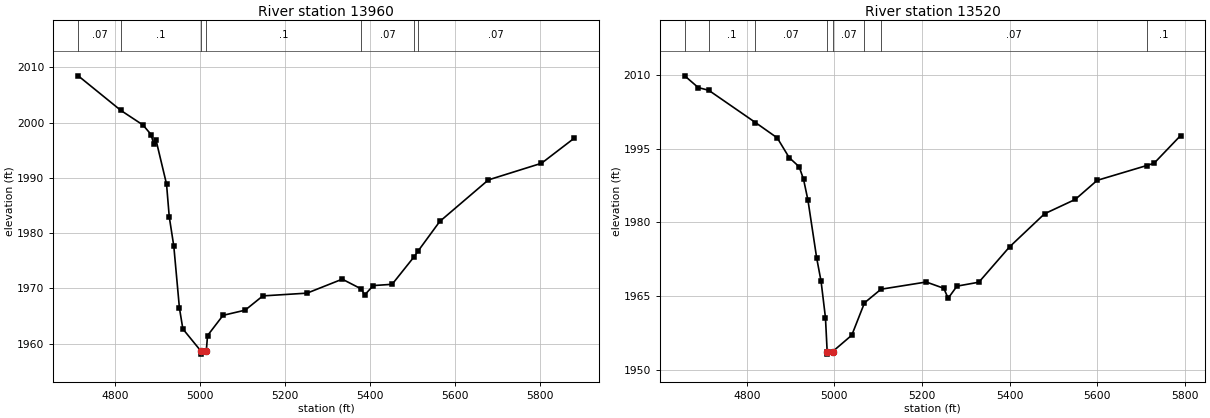
Type RM Length L Ch R = 1 ,13960   ,440,440,440
BEGIN DESCRIPTION:
Buffalo Creek 30.0
END DESCRIPTION:
XS GIS Cut Line= 3
      1845777.93     13903464.46        1845875.       13903725.
      1846728.92      13903967.8
#Sta/Elev= 30
  4714.2 2008.48  4814.6 2002.21  4866.4 1999.58  4885.5 1997.85  4891.4 1996.18
  4896.8 1996.95  4921.8 1988.89  4928.2 1982.96  4938.9 1977.65  4952.1 1966.46
  4960.2 1962.66  5003.2  1958.6  5003.7  1958.1  5015.2  1958.6  5018.2 1961.46
  5054.6 1965.12  5106.6 1966.06  5148.2 1968.64  5252.1 1969.14  5334.9 1971.67
  5380.1 1969.88  5387.3 1968.79  5407.8 1970.51  5452.1 1970.74  5504.2 1975.77
  5513.5  1976.8  5564.1 1982.12  5678.4 1989.64  5803.2 1992.65    5880 1997.18
#Mann= 7 ,-1 , 0
  4714.2     .07       0  4814.6      .1       0  5003.2     .05       0
  5015.2      .1       0  5380.1     .07       0  5504.2    .035       0
  5513.5     .07       0
Bank Sta=5003.2,5015.2
XS Rating Curve= 0 ,0
Exp/Cntr=0.3,0.1

Type RM Length L Ch R = 1 ,13520   ,449,449,449
BEGIN DESCRIPTION:
Buffalo Creek 29.0
END DESCRIPTION:
XS GIS Cut Line= 3
      1845583.96     13904091.96        1845925.       13904075.
      1846715.47     13904054.42
#Sta/Elev= 30
  4658.2 2009.85  4689.3 2007.45    4713 2006.91  4819.7 2000.34  4869.5 1997.21
  4896.7  1993.2  4919.6 1991.32  4929.6 1988.75  4939.6 1984.53  4959.6 1972.71
  4969.6 1967.98  4979.6 1960.57  4983.5 1953.66    4984 1953.16  4995.7 1953.66
  5039.7 1957.02  5068.7 1963.61  5106.4 1966.38  5209.7 1967.85  5249.7 1966.57
  5259.7 1964.54  5279.8 1967.01  5329.8 1967.81  5399.8    1975  5479.8 1981.75
  5549.8 1984.67  5599.9 1988.56  5713.2 1991.58  5729.9 1992.05  5790.4 1997.69
#Mann= 8 ,-1 , 0
  4658.2     .07       0    4713      .1       0  4819.7     .07       0
  4983.5     .05       0  4995.7     .07       0  5068.7      .1       0
  5106.4     .07       0  5713.2      .1       0
Bank Sta=4983.5,4995.7
XS Rating Curve= 0 ,0
Exp/Cntr=0.3,0.1