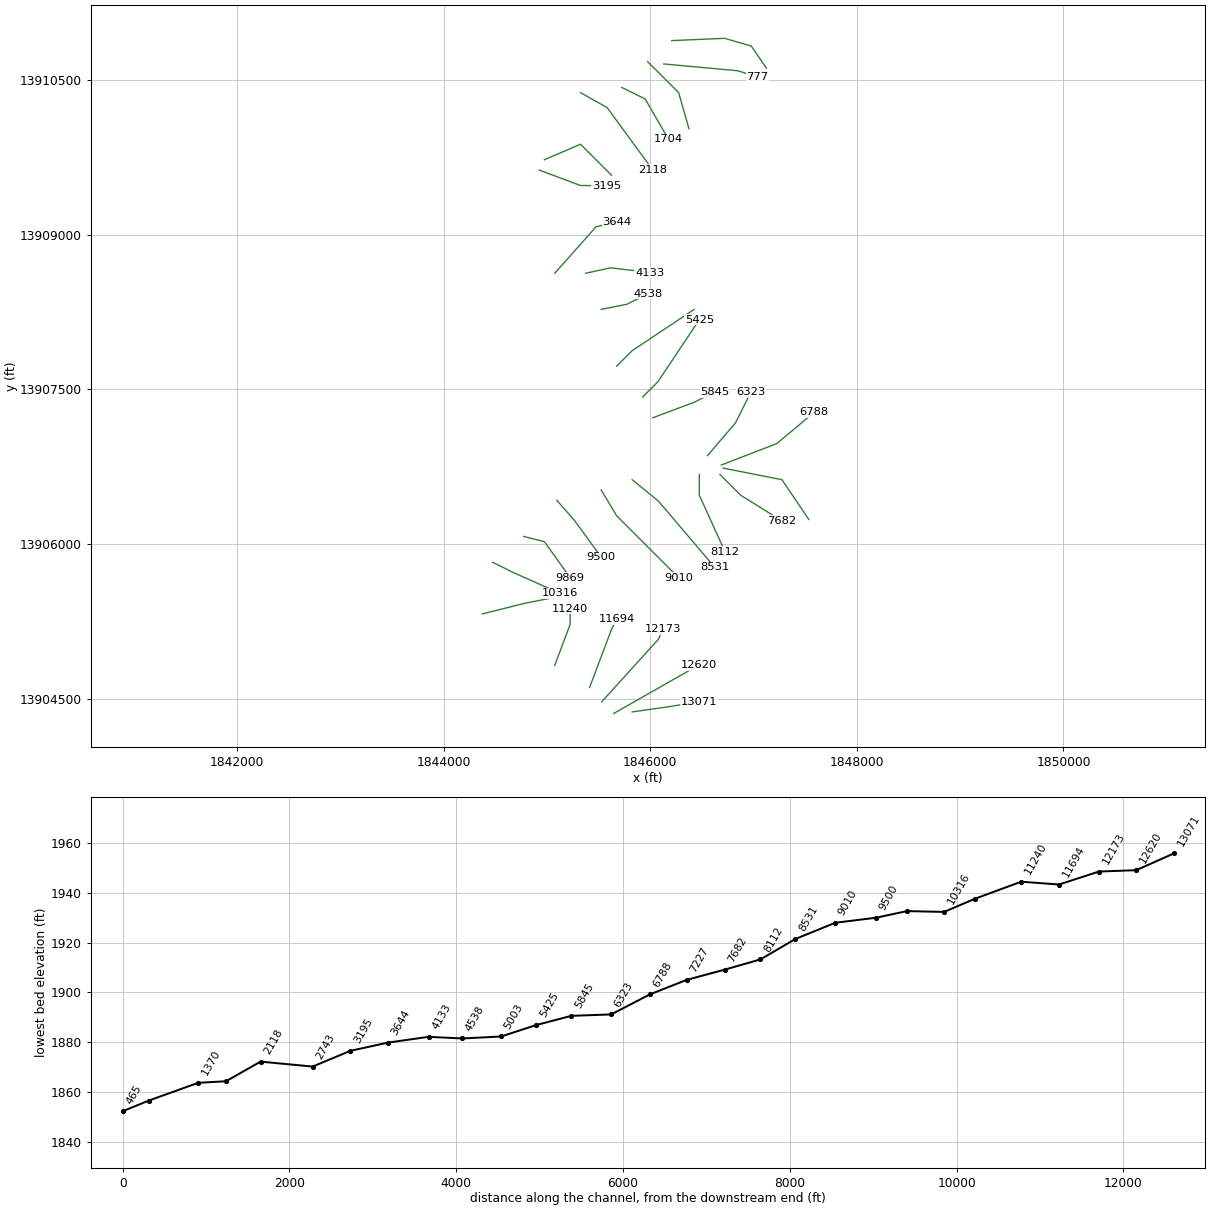
HEC-RAS study Buffalo Creek.prj: Buffalo Creek Base Level Engineering

--- Buffalo Creek.g01 (geometry) --- (continued)

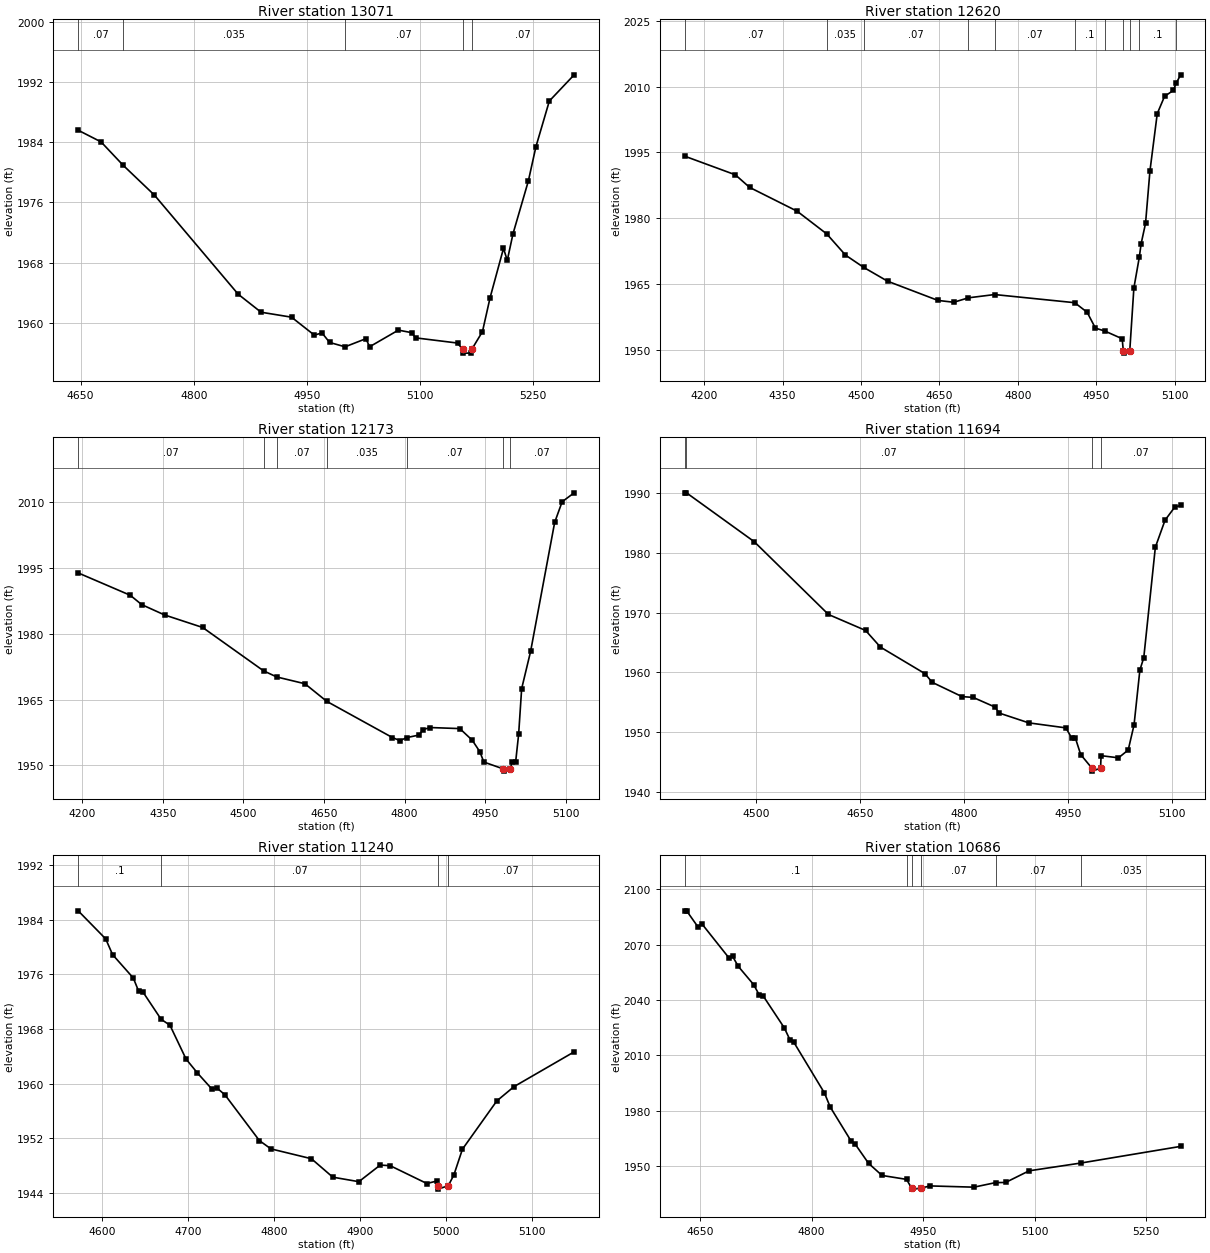
Type RM Length L Ch R = 1 ,13071   ,451,451,451
BEGIN DESCRIPTION:
Buffalo Creek 28.0
END DESCRIPTION:
XS GIS Cut Line= 3
      1845824.96     13904374.99        1846175.       13904425.
      1846474.97     13904474.99
#Sta/Elev= 30
  4646.8 1985.59  4677.1 1984.04  4706.2 1980.95  4747.9 1976.96    4859 1963.78
  4889.3 1961.39  4929.7 1960.73    4960 1958.34  4970.1 1958.64  4980.2 1957.37
  5000.7 1956.79  5028.3 1957.87  5033.3  1956.8  5071.4 1959.01  5089.1 1958.67
  5094.2 1957.98  5149.9 1957.29  5156.5 1956.45    5157 1955.95  5168.2 1955.95
  5168.7 1956.45  5182.9 1958.81    5193 1963.32  5210.8 1969.88  5215.8 1968.28
  5223.4 1971.82  5243.7 1978.82  5253.8  1983.4  5271.6 1989.48  5304.5 1992.96
#Mann= 5 ,-1 , 0
  4646.8     .07       0  4706.2    .035       0  5000.7     .07       0
  5156.5     .05       0  5168.7     .07       0
Bank Sta=5156.5,5168.7
XS Rating Curve= 0 ,0
Exp/Cntr=0.3,0.1

Type RM Length L Ch R = 1 ,12620   ,447,447,447
BEGIN DESCRIPTION:
Buffalo Creek 27.0
END DESCRIPTION:
XS GIS Cut Line= 3
      1845647.65     13904361.03        1846375.       13904775.
        1846475.       13904825.
#Sta/Elev= 30
  4162.6 1994.12  4259.5 1989.87  4286.8    1987  4377.7 1981.57  4434.4 1976.38
  4470.2 1971.56  4505.1 1968.75  4550.8  1965.6  4647.1 1961.22  4677.3  1960.8
  4705.2 1961.81  4755.5 1962.56  4908.8  1960.7  4932.5 1958.52  4948.3  1954.9
  4966.3 1954.24  4999.5 1952.48  5001.7  1949.7  5002.2  1949.2    5014  1949.7
  5021.9 1964.07  5032.2 1971.02  5035.8 1974.19  5044.2  1978.8  5052.6 1990.73
  5066.6 2003.82  5080.6 2007.77  5097.3 2009.11  5102.8 2010.75  5111.3 2012.67
#Mann= 11 ,-1 , 0
  4162.6     .07       0  4434.4    .035       0  4505.1     .07       0
  4705.2      .1       0  4755.5     .07       0  4908.8      .1       0
  4966.3     .07       0  5001.7     .05       0    5014     .07       0
  5032.2      .1       0  5102.8     .07       0
Bank Sta=5001.7,5014
XS Rating Curve= 0 ,0
Exp/Cntr=0.3,0.1

Type RM Length L Ch R = 1 ,12173   ,479,479,479
BEGIN DESCRIPTION:
Buffalo Creek 26.0
END DESCRIPTION:
XS GIS Cut Line= 3
      1845530.01     13904473.08        1846075.       13905075.
        1846125.     13905175.01
#Sta/Elev= 30
  4192.2 1993.91  4289.2 1988.81  4310.4 1986.68    4353 1984.32    4424 1981.46
  4537.4 1971.56    4562 1970.16  4614.5 1968.61  4655.2 1964.59  4777.4 1956.33
  4791.6 1955.62  4803.9 1956.31  4827.5 1956.91  4834.2 1958.15  4848.4 1958.61
    4903 1958.37  4926.1 1955.73  4940.3  1953.1  4947.8 1950.73  4984.2 1949.16
  4984.7 1948.66  4996.5 1949.16  5000.8 1950.74    5007 1950.74  5012.6 1957.09
  5018.2 1967.48  5034.9 1976.01  5079.7 2005.44  5093.6 2010.16    5116  2012.2
#Mann= 7 ,-1 , 0
  4192.2     .07       0  4537.4    .035       0    4562     .07       0
  4655.2    .035       0  4803.9     .07       0  4984.2     .05       0
  4996.5     .07       0
Bank Sta=4984.2,4996.5
XS Rating Curve= 0 ,0
Exp/Cntr=0.3,0.1

Type RM Length L Ch R = 1 ,11694   ,454,454,454
BEGIN DESCRIPTION:
Buffalo Creek 25.0
END DESCRIPTION:
XS GIS Cut Line= 3
      1845412.29     13904611.21        1845625.       13905175.
      1845675.01     13905275.01
#Sta/Elev= 30
  4397.4 1990.09    4400 1990.09  4497.6  1981.9  4604.5  1969.7    4658 1967.02
  4679.4 1964.23  4743.5 1959.78    4754 1958.32  4796.9 1955.93  4812.9  1955.8
  4844.6 1954.17  4850.3 1953.18  4893.1 1951.53  4946.5 1950.69  4954.7 1949.04
    4960 1949.06  4967.9 1946.21    4984 1943.94  4984.5 1943.44  4996.4 1943.94
  4997.3 1946.03  5022.3 1945.67  5036.3 1946.98  5044.7 1951.18  5053.1 1960.38
  5058.7 1962.44  5075.4 1980.97  5089.4 1985.51  5103.4  1987.7  5111.8 1987.97
#Mann= 4 ,-1 , 0
  4397.4      .1       0    4400     .07       0    4984     .05       0
  4996.4     .07       0
Bank Sta=4984,4996.4
XS Rating Curve= 0 ,0
Exp/Cntr=0.3,0.1

Type RM Length L Ch R = 1 ,11240   ,554,554,554
BEGIN DESCRIPTION:
Buffalo Creek 24.0
END DESCRIPTION:
XS GIS Cut Line= 3
      1845075.01     13904825.03        1845225.       13905225.
        1845225.     13905375.03
#Sta/Elev= 30
  4572.4 1985.29  4604.4 1981.18  4612.4 1978.88  4636.5 1975.46  4642.7 1973.54
    4648 1973.36  4668.8 1969.43  4679.2 1968.54  4697.9  1963.6  4711.2 1961.55
  4728.1 1959.19  4733.5 1959.41  4743.3 1958.34  4783.3 1951.66  4796.7 1950.45
  4843.8 1949.01  4868.7 1946.31    4899 1945.65  4923.9 1948.08  4935.5 1947.99
  4978.2 1945.38  4989.8 1945.75  4990.7 1945.06  4991.2 1944.56  5003.1 1945.06
  5009.6 1946.63  5019.6 1950.41  5059.6 1957.47  5079.6 1959.56  5149.6 1964.65
#Mann= 4 ,-1 , 0
  4572.4      .1       0  4668.8     .07       0  4990.7     .05       0
  5003.1     .07       0
Bank Sta=4990.7,5003.1
XS Rating Curve= 0 ,0
Exp/Cntr=0.3,0.1

Type RM Length L Ch R = 1 ,10686   ,370,370,370
BEGIN DESCRIPTION:
Buffalo Creek 23.0
END DESCRIPTION:
XS GIS Cut Line= 3
      1844375.01       13905325.      1844783.94     13905427.19
      1845025.04     13905475.01
#Sta/Elev= 30
  4629.2 2088.21  4631.8 2088.21  4647.2 2079.45  4652.4 2081.15  4688.5 2062.89
  4693.6 2063.64  4701.3 2058.18    4722 2048.31  4729.7  2042.6  4734.9 2042.14
  4763.2 2024.96    4771 2018.35  4776.1 2017.11  4817.3 1989.68    4825 1982.13
  4853.4 1963.53  4858.6 1962.06  4876.6 1951.68  4894.7 1945.12  4927.7 1942.99
  4934.6 1938.22  4935.1 1937.72  4947.5 1938.22    4959 1939.46  5018.4 1938.78
  5047.6 1941.25    5061 1941.32  5092.6 1947.62  5162.4 1951.84  5296.5 1960.83
#Mann= 6 ,-1 , 0
  4629.2      .1       0  4927.7     .07       0  4934.6     .05       0
  4947.5     .07       0  5047.6     .07       0  5162.4    .035       0
Bank Sta=4934.6,4947.5
XS Rating Curve= 0 ,0
Exp/Cntr=0.3,0.1

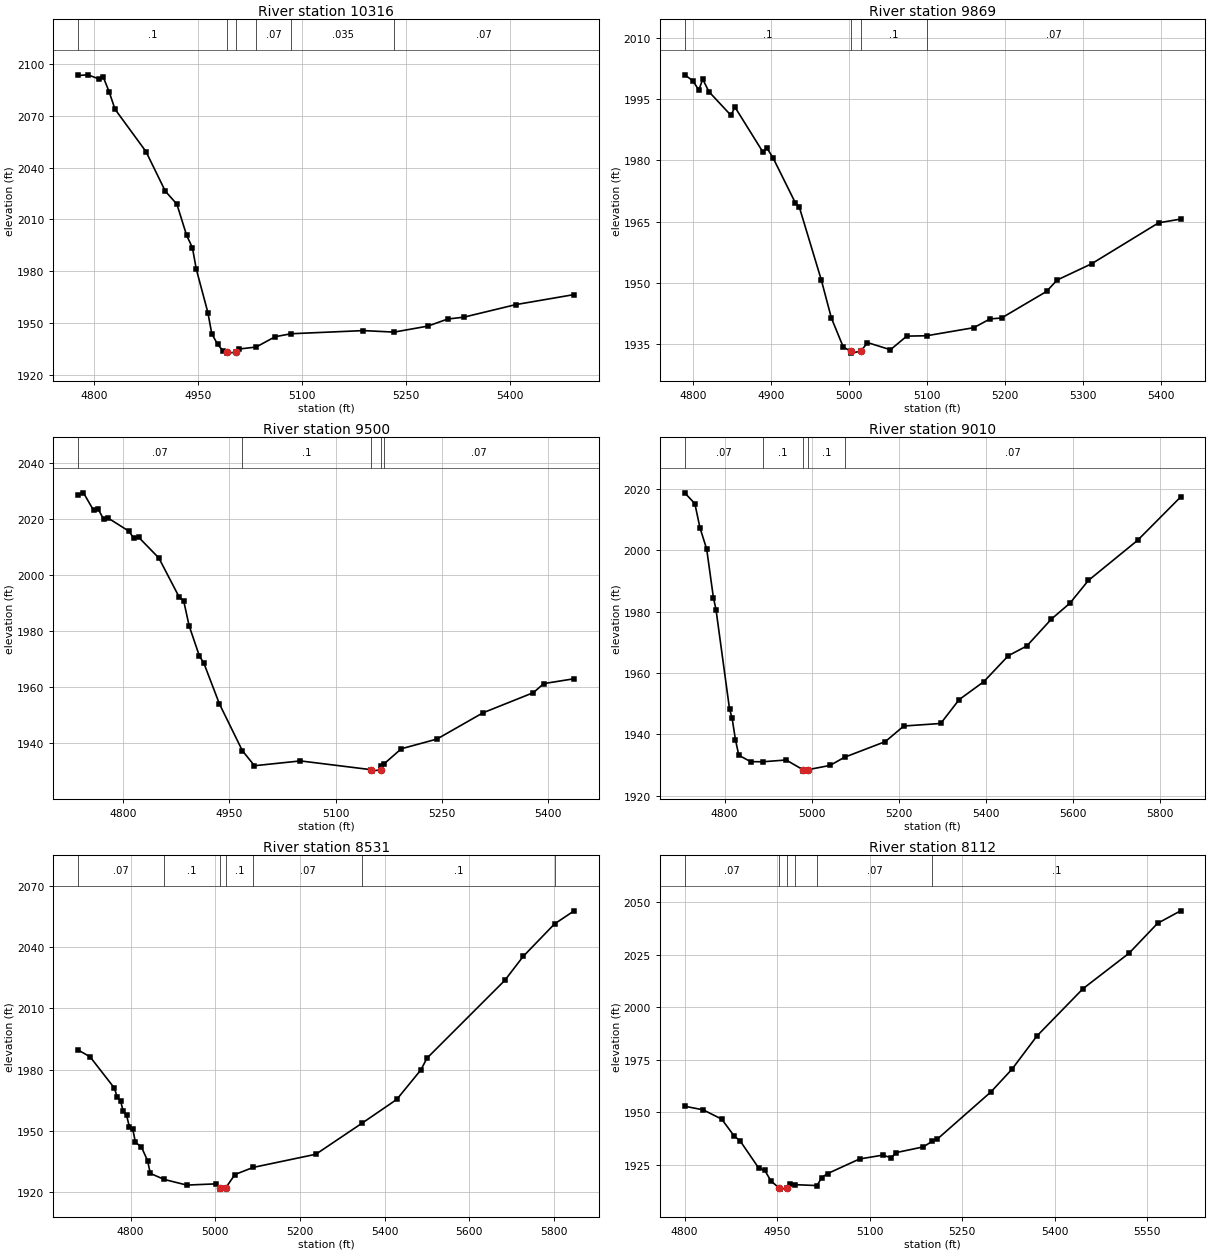
Type RM Length L Ch R = 1 ,10316   ,447,447,447
BEGIN DESCRIPTION:
Buffalo Creek 22.0
END DESCRIPTION:
XS GIS Cut Line= 3
      1844475.04     13905824.98        1844675.       13905725.
        1845125.       13905525.
#Sta/Elev= 30
  4776.5 2093.39  4790.4 2093.78  4807.2  2091.3  4812.8 2092.33  4821.2  2083.9
  4829.6 2073.85  4874.3  2049.3  4902.2 2026.36    4919 2018.74    4933 2000.73
  4941.4 1993.53    4947 1981.04  4963.7 1955.93  4969.3 1943.73  4977.7 1937.52
  4986.1 1933.47  4990.8 1932.92  4991.3 1932.42  5003.7 1932.92    5009 1934.82
  5033.3 1935.94  5060.9 1941.94  5083.9 1943.66  5188.1 1945.48  5232.6 1944.61
  5281.2 1948.08  5309.9 1952.19  5333.1 1953.26  5408.4 1960.56  5492.5 1966.37
#Mann= 6 ,-1 , 0
  4776.5      .1       0  4990.8     .05       0  5003.7      .1       0
  5033.3     .07       0  5083.9    .035       0  5232.6     .07       0
Bank Sta=4990.8,5003.7
XS Rating Curve= 0 ,0
Exp/Cntr=0.3,0.1

Type RM Length L Ch R = 1 ,9869    ,369,369,369
BEGIN DESCRIPTION:
Buffalo Creek 21.0
END DESCRIPTION:
XS GIS Cut Line= 3
      1844774.95     13906075.01        1844975.       13906025.
      1845224.99     13905675.02
#Sta/Elev= 30
  4789.3 2000.98  4799.7 1999.54  4807.4 1997.26  4812.5  1999.9  4820.3 1996.87
  4848.6 1991.06  4853.8 1993.06  4889.8    1982    4895 1982.97  4902.7 1980.61
  4931.1 1969.66  4936.2 1968.66  4964.6 1950.66  4977.5 1941.35  4992.9 1934.16
  5002.5 1933.23    5003 1932.73  5015.5 1933.23  5023.8 1935.32  5053.3 1933.56
  5074.2  1936.9  5099.7 1936.99  5160.2 1938.97  5181.1 1941.12  5195.8 1941.34
  5253.6 1947.86  5267.1 1950.65  5311.3 1954.63  5397.4 1964.69  5425.6  1965.6
#Mann= 4 ,-1 , 0
  4789.3      .1       0  5002.5     .05       0  5015.5      .1       0
  5099.7     .07       0
Bank Sta=5002.5,5015.5
XS Rating Curve= 0 ,0
Exp/Cntr=0.3,0.1

Type RM Length L Ch R = 1 ,9500    ,490,490,490
BEGIN DESCRIPTION:
Buffalo Creek 20.0
END DESCRIPTION:
XS GIS Cut Line= 3
      1845095.23     13906425.71      1845265.26     13906231.53
      1845524.99     13905875.01
#Sta/Elev= 30
  4737.2 2028.69  4744.6 2029.52  4758.9 2023.24  4765.5 2023.62  4773.1 2020.07
  4779.7 2020.45  4808.2 2015.89  4815.8 2013.28  4822.4 2013.65  4850.9 2006.23
  4879.4 1992.33    4886  1990.8  4893.6 1981.99  4907.9 1971.32  4914.5 1968.55
  4936.3 1954.09  4968.6 1937.39  4985.7 1932.01  5050.5 1933.73  5150.6 1930.58
  5151.1 1930.08  5163.7 1930.58  5164.2 1932.04  5168.9 1932.79  5192.7 1938.07
  5242.9 1941.53  5307.8 1950.91  5378.9 1958.12  5393.5 1961.35  5436.4 1963.09
#Mann= 5 ,-1 , 0
  4737.2     .07       0  4968.6      .1       0  5150.6     .05       0
  5163.7      .1       0  5168.9     .07       0
Bank Sta=5150.6,5163.7
XS Rating Curve= 0 ,0
Exp/Cntr=0.3,0.1

Type RM Length L Ch R = 1 ,9010    ,479,479,479
BEGIN DESCRIPTION:
Buffalo Creek 19.0
END DESCRIPTION:
XS GIS Cut Line= 3
      1845524.98     13906525.03        1845675.       13906275.
      1846274.99     13905675.01
#Sta/Elev= 30
  4708.2 2018.79  4731.6 2015.27  4743.2 2007.46  4758.8 2000.43  4774.3 1984.57
  4780.2 1980.73  4811.3  1948.3  4817.1  1945.4  4824.9 1938.31  4832.6 1933.22
  4859.8 1931.13  4887.8 1931.09  4941.5 1931.67  4979.6 1928.54  4980.1 1928.04
  4992.7 1928.54  5042.2  1929.9  5076.1 1932.59  5169.5 1937.67  5211.9 1942.75
  5296.8 1943.58  5339.2 1951.36  5395.8  1957.2  5452.3 1965.68  5494.8 1968.86
  5551.3 1977.63  5593.8  1982.8  5636.2 1990.21  5749.3 2003.29  5848.3 2017.43
#Mann= 5 ,-1 , 0
  4708.2     .07       0  4887.8      .1       0  4979.6     .05       0
  4992.7      .1       0  5076.1     .07       0
Bank Sta=4979.6,4992.7
XS Rating Curve= 0 ,0
Exp/Cntr=0.3,0.1

Type RM Length L Ch R = 1 ,8531    ,419,419,419
BEGIN DESCRIPTION:
Buffalo Creek 18.0
END DESCRIPTION:
XS GIS Cut Line= 3
      1845824.97     13906625.03      1846079.19     13906417.76
      1846624.97     13905775.03
#Sta/Elev= 30
  4676.5 1989.57  4704.5 1986.26    4762 1970.93  4768.4  1966.6  4776.4  1964.8
  4782.8 1959.58  4790.7 1957.67  4797.2 1952.11  4805.1 1951.11  4811.5 1944.49
  4825.9 1942.03  4840.3 1935.45  4846.7 1929.21  4879.3 1926.26  4932.9 1923.48
  5002.7 1924.08  5011.3    1922  5011.8  1921.5  5024.5    1922  5046.5 1928.63
  5089.5 1932.12  5237.6 1938.56  5347.4 1953.86  5428.7 1965.39  5485.8 1979.87
  5500.1 1985.59  5683.8 2023.65  5727.5 2035.44  5801.5 2051.32  5847.7 2057.71
#Mann= 7 ,-1 , 0
  4676.5     .07       0  4879.3      .1       0  5011.3     .05       0
  5024.5      .1       0  5089.5     .07       0  5347.4      .1       0
  5801.5     .07       0
Bank Sta=5011.3,5024.5
XS Rating Curve= 0 ,0
Exp/Cntr=0.3,0.1

Type RM Length L Ch R = 1 ,8112    ,430,430,430
BEGIN DESCRIPTION:
Buffalo Creek 17.0
END DESCRIPTION:
XS GIS Cut Line= 3
        1846475.     13906675.04        1846475.       13906475.
        1846725.     13905924.99
#Sta/Elev= 30
  4800.1 1952.78  4830.1 1951.06  4860.1 1946.64  4880.1  1938.7  4890.1 1936.22
  4920.1 1923.35  4930.1 1922.17  4940.1 1917.13  4953.5 1913.79    4954 1913.29
  4966.7 1913.79  4970.1 1915.92  4978.8 1915.42  5014.8 1914.98  5022.1 1918.78
    5032 1920.71  5083.6 1927.65    5121 1929.47  5135.2 1928.25  5142.9 1930.69
  5186.9  1933.4  5201.2 1936.01  5209.9 1937.16  5296.7  1959.6  5330.8  1970.4
  5371.4 1986.28  5446.1  2008.8  5520.8  2025.7  5566.9 2039.91  5604.3 2045.87
#Mann= 6 ,-1 , 0
  4800.1     .07       0  4953.5     .05       0  4966.7     .07       0
  4978.8      .1       0  5014.8     .07       0  5201.2      .1       0
Bank Sta=4953.5,4966.7
XS Rating Curve= 0 ,0
Exp/Cntr=0.3,0.1

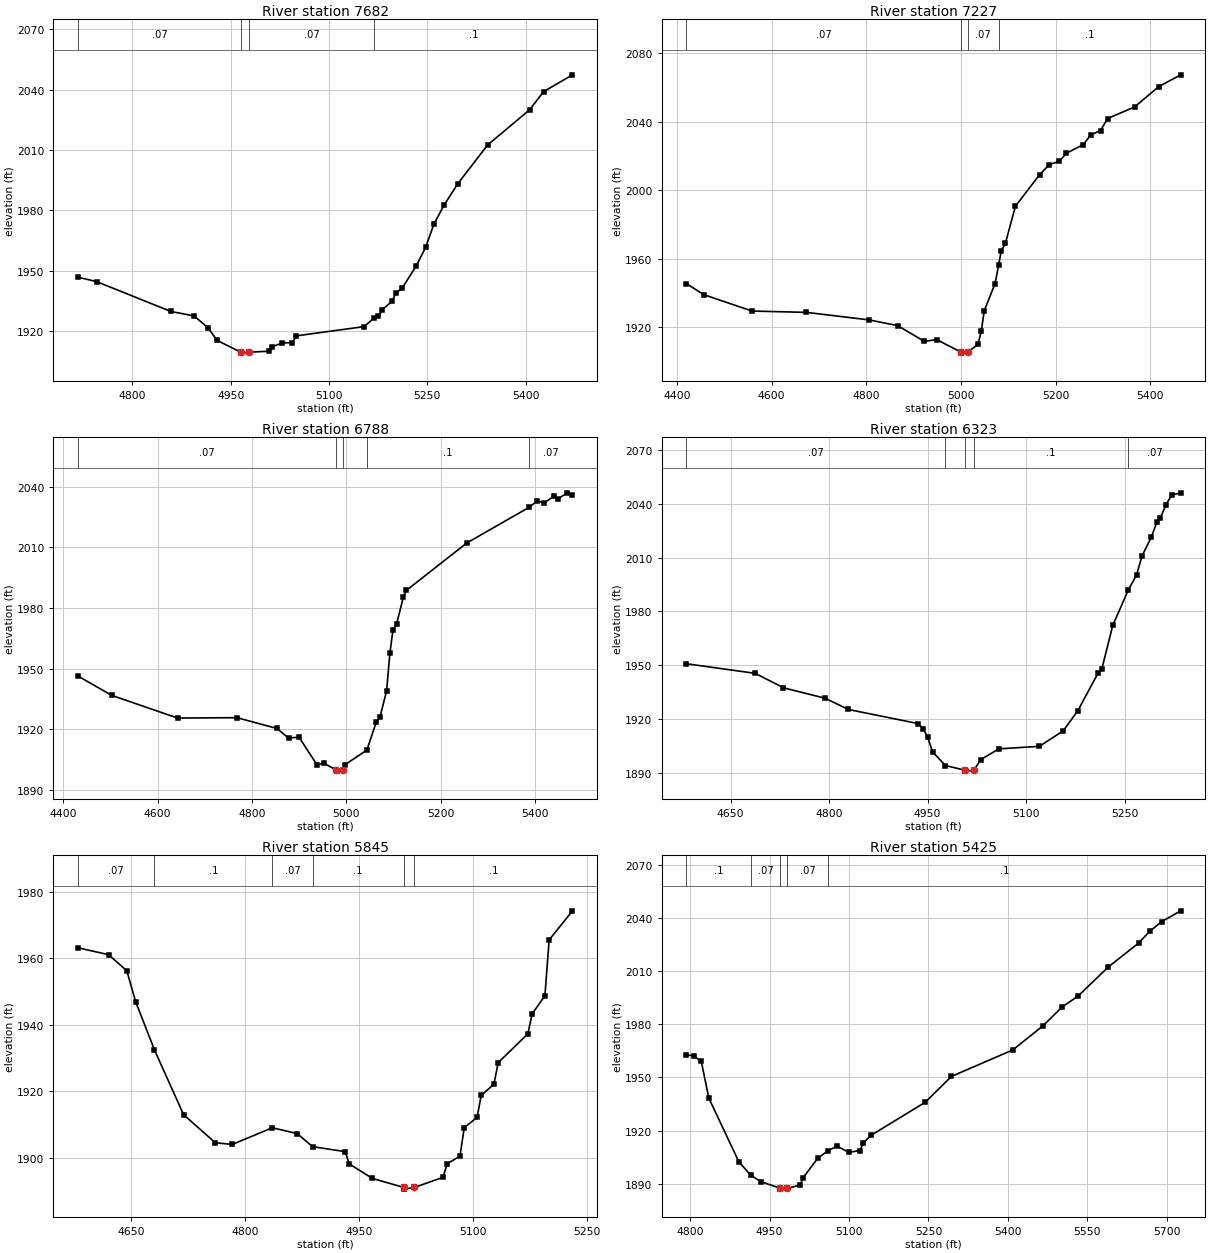
Type RM Length L Ch R = 1 ,7682    ,455,455,455
BEGIN DESCRIPTION:
Buffalo Creek 16.0
END DESCRIPTION:
XS GIS Cut Line= 3
      1846674.97     13906675.03        1846875.       13906475.
      1847275.01     13906224.99
#Sta/Elev= 30
  4717.1 1946.84  4745.4 1944.67  4858.6 1929.86  4893.9 1927.65  4915.1 1921.86
  4929.3 1915.49  4965.1 1909.67  4965.6 1909.17  4978.3 1909.67  5007.7 1910.08
  5013.6 1912.39  5028.9 1914.26  5044.2 1914.36  5050.1 1917.74  5153.3 1922.32
  5168.8 1926.54  5175.1 1927.42    5181 1930.64  5196.3 1934.95  5202.2 1938.97
  5211.7 1941.46  5232.9  1952.3  5247.6  1961.7    5260 1973.11  5275.3 1982.48
  5296.6 1993.25    5342 2012.47  5406.2 2029.95  5427.5 2038.95  5471.7 2047.34
#Mann= 4 ,-1 , 0
  4717.1     .07       0  4965.1     .05       0  4978.3     .07       0
  5168.8      .1       0
Bank Sta=4965.1,4978.3
XS Rating Curve= 0 ,0
Exp/Cntr=0.3,0.1

Type RM Length L Ch R = 1 ,7227    ,439,439,439
BEGIN DESCRIPTION:
Buffalo Creek 15.0
END DESCRIPTION:
XS GIS Cut Line= 3
      1846706.04     13906737.39        1847275.       13906625.
       1847535.1     13906239.97
#Sta/Elev= 30
  4419.8 1945.65  4456.2  1939.2  4558.7 1929.59  4673.6 1928.82  4806.1 1924.42
  4866.4 1921.09  4922.8 1911.89  4948.8 1912.96  5000.6 1905.55  5001.1 1905.05
  5013.9 1905.55    5036 1910.12  5043.2  1918.1  5049.2 1929.75  5072.2 1945.66
  5079.6 1956.29  5085.2 1964.55  5094.1 1969.24  5115.1  1990.7  5166.1 2009.07
  5187.1 2015.06  5208.1 2016.94    5223 2021.69    5259 2026.73    5274 2032.31
    5295 2034.87  5309.9  2041.9  5366.9 2048.65  5417.8 2060.47  5464.4 2067.39
#Mann= 4 ,-1 , 0
  4419.8     .07       0  5000.6     .05       0  5013.9     .07       0
  5079.6      .1       0
Bank Sta=5000.6,5013.9
XS Rating Curve= 0 ,0
Exp/Cntr=0.3,0.1

Type RM Length L Ch R = 1 ,6788    ,465,465,465
BEGIN DESCRIPTION:
Buffalo Creek 14.0
END DESCRIPTION:
XS GIS Cut Line= 3
      1846688.56     13906767.65        1847225.       13906975.
      1847586.97     13907277.88
#Sta/Elev= 30
  4431.7 1946.23  4502.9 1936.71  4642.3  1925.5  4768.3 1925.68  4852.8 1920.34
  4877.4 1915.62  4899.6 1916.02  4937.3 1902.51  4953.2 1903.03  4978.6 1899.74
  4979.1 1899.24  4992.2 1899.74  4997.2 1902.45  5043.3 1909.66  5063.4 1923.65
  5071.2 1926.16  5085.1 1938.91  5092.1 1957.85  5098.6  1969.1  5106.4 1972.19
  5120.7 1985.42  5127.2 1988.69  5254.7 2012.08  5387.4  2029.8  5404.4 2032.95
  5418.7  2031.9  5439.5 2035.23  5447.3 2033.84  5468.1 2036.92  5478.8 2035.87
#Mann= 5 ,-1 , 0
  4431.7     .07       0  4978.6     .05       0  4992.2     .07       0
  5043.3      .1       0  5387.4     .07       0
Bank Sta=4978.6,4992.2
XS Rating Curve= 0 ,0
Exp/Cntr=0.3,0.1

Type RM Length L Ch R = 1 ,6323    ,478,478,478
BEGIN DESCRIPTION:
Buffalo Creek 13.0
END DESCRIPTION:
XS GIS Cut Line= 3
       1846553.7     13906857.96        1846825.       13907175.
      1846975.01     13907475.01
#Sta/Elev= 30
  4582.7 1950.93  4687.7 1945.57  4730.5 1937.55  4794.2 1931.71  4829.3 1925.48
  4935.8 1917.61  4943.4 1914.72    4950  1910.1  4957.7 1901.87  4977.1 1894.29
  5007.1 1891.67  5007.6 1891.17  5020.8 1891.67  5030.7 1897.54  5058.7 1903.57
  5120.2 1904.97  5156.5 1913.57  5178.9 1924.87  5209.6 1945.76  5215.2 1947.86
    5232 1972.28  5255.4 1991.75  5268.3 2000.49  5276.7 2011.08  5290.7 2021.36
    5299 2029.61  5304.6 2032.23    5313 2039.36  5321.4 2044.72  5335.4 2046.03
#Mann= 5 ,-1 , 0
  4582.7     .07       0  4977.1      .1       0  5007.1     .05       0
  5020.8      .1       0  5255.4     .07       0
Bank Sta=5007.1,5020.8
XS Rating Curve= 0 ,0
Exp/Cntr=0.3,0.1

Type RM Length L Ch R = 1 ,5845    ,420,420,420
BEGIN DESCRIPTION:
Buffalo Creek 12.0
END DESCRIPTION:
XS GIS Cut Line= 3
      1846024.97     13907224.99        1846425.       13907375.
      1846624.96     13907474.98
#Sta/Elev= 30
  4580.1 1963.16  4620.2 1961.09  4644.2 1956.26  4655.8 1946.96  4680.6 1932.46
    4719 1912.96  4760.8 1904.54  4783.1 1904.04  4835.7 1909.05  4868.5 1907.31
  4888.7 1903.37  4931.7 1901.88    4937 1898.19  4967.3 1893.83  5008.9  1891.1
  5009.4  1890.6  5022.6  1891.1  5060.4 1894.14    5066 1898.24  5082.8 1900.51
  5088.4 1909.08  5105.2 1912.14  5110.8  1918.8  5127.5 1922.17  5133.1 1928.63
  5172.2 1937.31  5177.8 1943.28  5194.6 1948.77  5200.2 1965.54  5230.9 1974.28
#Mann= 6 ,-1 , 0
  4580.1     .07       0  4680.6      .1       0  4835.7     .07       0
  4888.7      .1       0  5008.9     .05       0  5022.6      .1       0
Bank Sta=5008.9,5022.6
XS Rating Curve= 0 ,0
Exp/Cntr=0.3,0.1

Type RM Length L Ch R = 1 ,5425    ,422,422,422
BEGIN DESCRIPTION:
Buffalo Creek 11.0
END DESCRIPTION:
XS GIS Cut Line= 3
      1845925.03     13907425.03        1846075.       13907575.
        1846475.       13908175.
#Sta/Elev= 30
    4793 1962.83  4807.1 1962.18  4821.2  1959.1  4835.4 1938.37  4891.9 1902.49
  4914.6 1894.67  4934.4 1891.07  4969.9  1887.4  4970.4  1886.9  4983.7  1887.4
  5008.1 1889.15  5012.6 1893.04  5041.1 1904.35  5060.4 1908.59  5077.2  1911.2
  5099.7  1907.7  5120.8 1908.68  5126.8 1912.94  5141.8 1917.34    5244 1936.02
  5293.5  1950.6  5409.2 1965.56  5466.3 1979.22  5502.3 1989.84  5532.4    1996
  5589.5 2012.45  5646.6 2025.94  5667.6 2032.59  5690.1 2038.05  5726.2  2044.2
#Mann= 5 ,-1 , 0
    4793      .1       0  4914.6     .07       0  4969.9     .05       0
  4983.7     .07       0  5060.4      .1       0
Bank Sta=4969.9,4983.7
XS Rating Curve= 0 ,0
Exp/Cntr=0.3,0.1

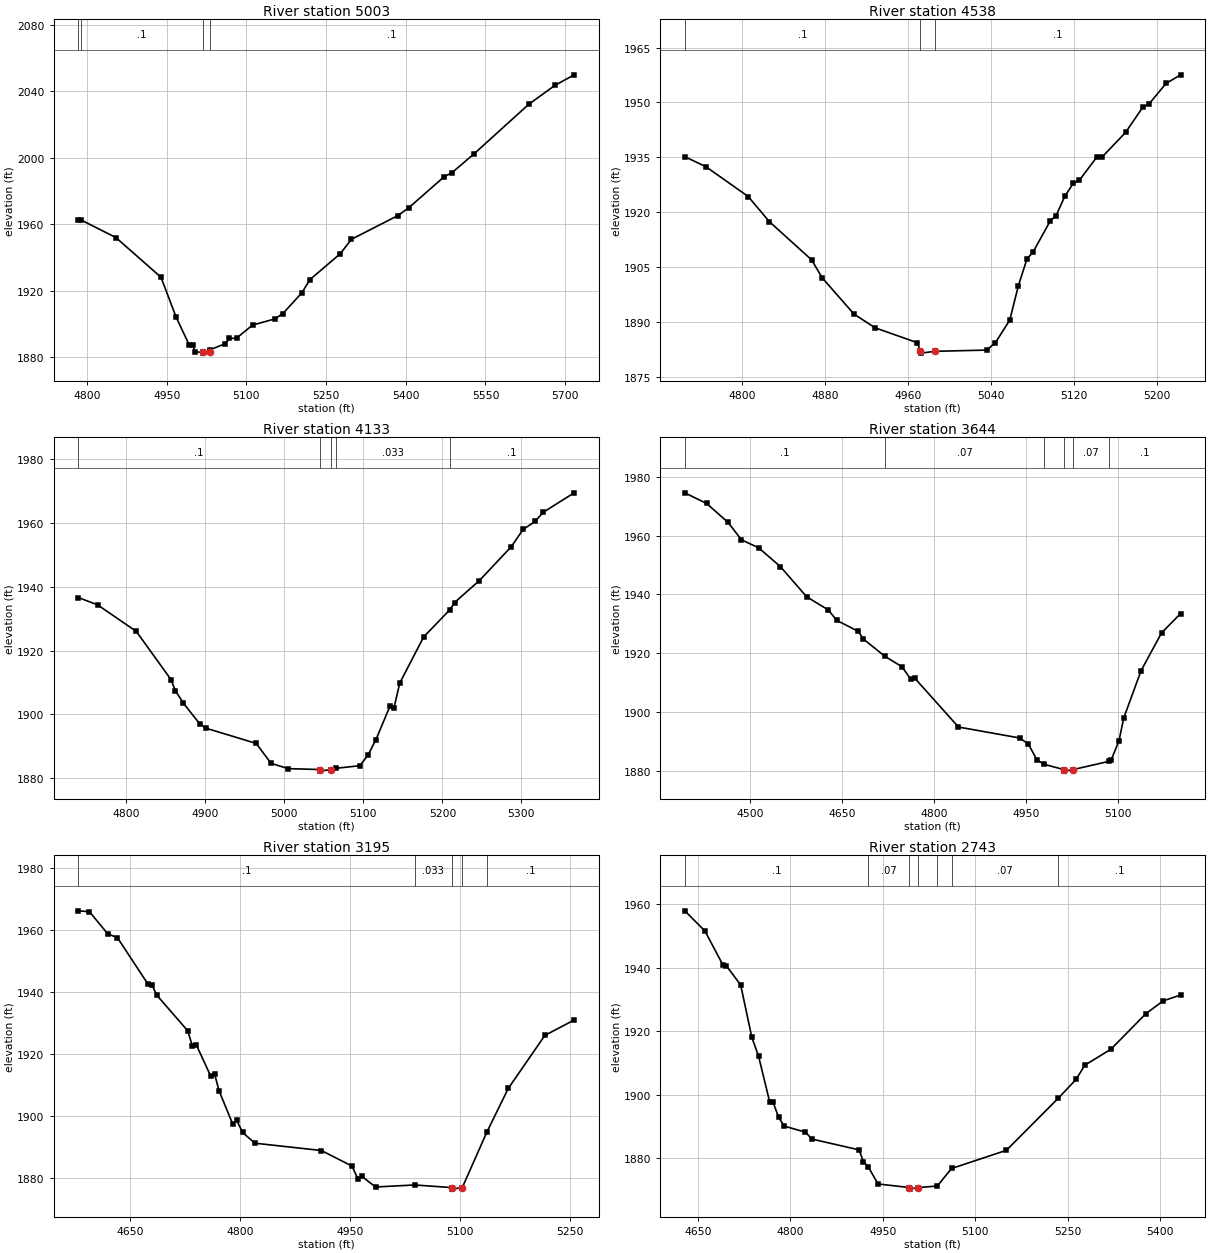
Type RM Length L Ch R = 1 ,5003    ,465,465,465
BEGIN DESCRIPTION:
Buffalo Creek 10.0
END DESCRIPTION:
XS GIS Cut Line= 3
      1845674.97     13907724.97        1845825.       13907875.
      1846425.01     13908275.01
#Sta/Elev= 30
  4783.6 1962.74  4789.4 1962.43  4854.4 1951.93  4939.2    1928  4967.5 1904.12
  4992.2 1887.31  4998.8 1887.31  5003.3 1883.03  5017.4 1882.79  5017.9 1882.29
  5031.2 1882.79  5031.8 1884.38  5060.4 1888.01  5067.9 1891.13  5081.4 1891.31
  5111.5 1899.19  5153.5 1902.91  5168.5 1906.09  5204.6 1918.75  5219.6 1926.61
  5276.7 1942.23  5297.7 1950.89  5384.9 1965.16  5405.9 1969.98    5472 1988.55
    5487 1991.06  5529.1 2002.58  5631.3 2032.23  5680.8 2043.69  5716.9 2050.02
#Mann= 4 ,-1 , 0
  4783.6     .07       0  4789.4      .1       0  5017.4     .05       0
  5031.2      .1       0
Bank Sta=5017.4,5031.2
XS Rating Curve= 0 ,0
Exp/Cntr=0.3,0.1

Type RM Length L Ch R = 1 ,4538    ,405,405,405
BEGIN DESCRIPTION:
Buffalo Creek 9.0
END DESCRIPTION:
XS GIS Cut Line= 3
      1845525.01       13908275.        1845775.       13908325.
      1845975.04     13908425.02
#Sta/Elev= 30
  4744.6 1935.17    4765 1932.44  4805.8 1924.29  4826.2 1917.43    4867 1906.99
  4877.2 1902.08  4907.8  1892.2  4928.2 1888.43    4969 1884.35  4972.1    1882
  4972.6  1881.5  4986.1    1882  5035.9 1882.33  5044.3 1884.31  5058.2 1890.49
  5066.6 1899.92    5075 1907.35  5080.6 1909.02  5097.4 1917.65    5103 1919.08
  5111.3  1924.3  5119.7 1927.92  5125.3 1928.67  5142.1 1934.99  5147.7 1935.16
    5170 1941.79  5186.8 1948.74  5192.4 1949.48  5209.2  1955.2  5223.2 1957.54
#Mann= 3 ,-1 , 0
  4744.6      .1       0  4972.1     .05       0  4986.1      .1       0
Bank Sta=4972.1,4986.1
XS Rating Curve= 0 ,0
Exp/Cntr=0.3,0.1

Type RM Length L Ch R = 1 ,4133    ,489,489,489
BEGIN DESCRIPTION:
Buffalo Creek 8.0
END DESCRIPTION:
XS GIS Cut Line= 3
      1845375.01       13908625.      1845616.79     13908677.99
      1845994.11     13908632.25
#Sta/Elev= 30
  4739.2 1936.64  4763.7 1934.31  4812.6    1926  4856.4  1910.9    4862 1907.41
  4872.3 1903.45  4892.7 1897.04  4900.3 1895.66  4964.4 1890.84  4983.2 1884.57
  5005.1 1882.93  5044.7 1882.65  5045.2 1882.15  5058.7 1882.65  5065.6 1883.04
  5095.7 1883.86  5105.8 1887.17  5115.9 1892.03  5133.6  1902.5  5138.6 1901.89
  5146.1 1909.81  5176.3 1924.27  5209.7 1932.85  5215.4 1935.06  5246.8 1941.95
  5287.1 1952.56  5302.3 1958.02  5317.3  1960.5  5327.4 1963.34  5366.8 1969.49
#Mann= 5 ,-1 , 0
  4739.2      .1       0  5044.7     .05       0  5058.7      .1       0
  5065.6    .033       0  5209.7      .1       0
Bank Sta=5044.7,5058.7
XS Rating Curve= 0 ,0
Exp/Cntr=0.3,0.1

Type RM Length L Ch R = 1 ,3644    ,449,449,449
BEGIN DESCRIPTION:
Buffalo Creek 7.0
END DESCRIPTION:
XS GIS Cut Line= 3
      1845075.01     13908625.01        1845475.       13909075.
      1845674.97     13909124.99
#Sta/Elev= 30
  4393.3 1974.57  4428.8 1970.95    4464 1964.47  4485.7 1958.56  4513.7 1955.85
  4549.2 1949.43  4591.9 1939.19    4627 1934.71  4641.2 1931.13  4676.4 1927.36
  4683.9 1924.87  4719.7 1918.87  4747.4 1915.35  4761.6  1911.1  4768.3 1911.42
  4839.4 1894.83  4938.9 1891.12  4953.1 1889.12  4967.4  1883.6  4979.6 1882.11
  5011.5 1880.32    5012 1879.82  5025.6 1880.32  5084.4 1883.13  5088.1 1883.53
    5101 1890.09  5108.8 1897.92  5137.1 1914.06  5170.6 1926.94  5201.5 1933.48
#Mann= 6 ,-1 , 0
  4393.3      .1       0  4719.7     .07       0  4979.6     .07       0
  5011.5     .05       0  5025.6     .07       0  5084.4      .1       0
Bank Sta=5011.5,5025.6
XS Rating Curve= 0 ,0
Exp/Cntr=0.3,0.1

Type RM Length L Ch R = 1 ,3195    ,452,452,452
BEGIN DESCRIPTION:
Buffalo Creek 6.0
END DESCRIPTION:
XS GIS Cut Line= 3
      1844924.98     13909625.01        1845325.       13909475.
      1845574.98       13909475.
#Sta/Elev= 30
  4578.9 1966.19  4594.1  1965.9    4619 1958.79  4632.3 1957.54  4674.2 1942.51
  4679.5 1942.38  4685.7  1939.1  4728.4 1927.52  4734.7 1922.55    4740 1923.03
  4759.6 1912.98  4764.9 1913.67  4771.2 1908.15  4789.9 1897.41  4795.2 1898.73
  4803.2 1894.77  4820.1 1891.32  4910.9 1888.96  4952.7 1883.94  4960.7 1879.82
  4966.1 1880.65  4984.8 1877.21  5038.2 1877.86    5089 1877.02  5089.5 1876.52
  5103.3 1877.02  5136.8 1894.86  5166.1 1908.96  5216.1 1926.05  5256.1 1931.02
#Mann= 5 ,-1 , 0
  4578.9      .1       0  5038.2    .033       0    5089     .05       0
  5103.3    .033       0  5136.8      .1       0
Bank Sta=5089,5103.3
XS Rating Curve= 0 ,0
Exp/Cntr=0.3,0.1

Type RM Length L Ch R = 1 ,2743    ,625,625,625
BEGIN DESCRIPTION:
Buffalo Creek 5.0
END DESCRIPTION:
XS GIS Cut Line= 3
      1844974.99     13909724.99        1845325.       13909875.
      1845625.02     13909574.98
#Sta/Elev= 30
  4628.4 1957.88  4661.1 1951.53  4690.1  1940.9  4695.5 1940.65  4719.1 1934.53
  4737.2 1918.04  4748.1 1912.13  4766.2 1897.71  4771.7 1897.59  4780.7 1892.83
  4789.8 1890.05  4824.2 1888.15  4835.1 1885.95  4911.3 1882.56  4918.5 1878.84
  4926.3 1877.22  4942.1 1871.82    4993 1870.69  4993.5 1870.19  5007.3 1870.69
  5038.4 1871.17  5061.5 1876.69  5150.6 1882.42  5234.6 1898.79  5263.8 1904.78
  5277.9 1909.24  5320.3 1914.27  5376.9 1925.44  5405.2 1929.51  5433.5 1931.35
#Mann= 7 ,-1 , 0
  4628.4      .1       0  4926.3     .07       0    4993     .05       0
  5007.3     .07       0  5038.4      .1       0  5061.5     .07       0
  5234.6      .1       0
Bank Sta=4993,5007.3
XS Rating Curve= 0 ,0
Exp/Cntr=0.3,0.1

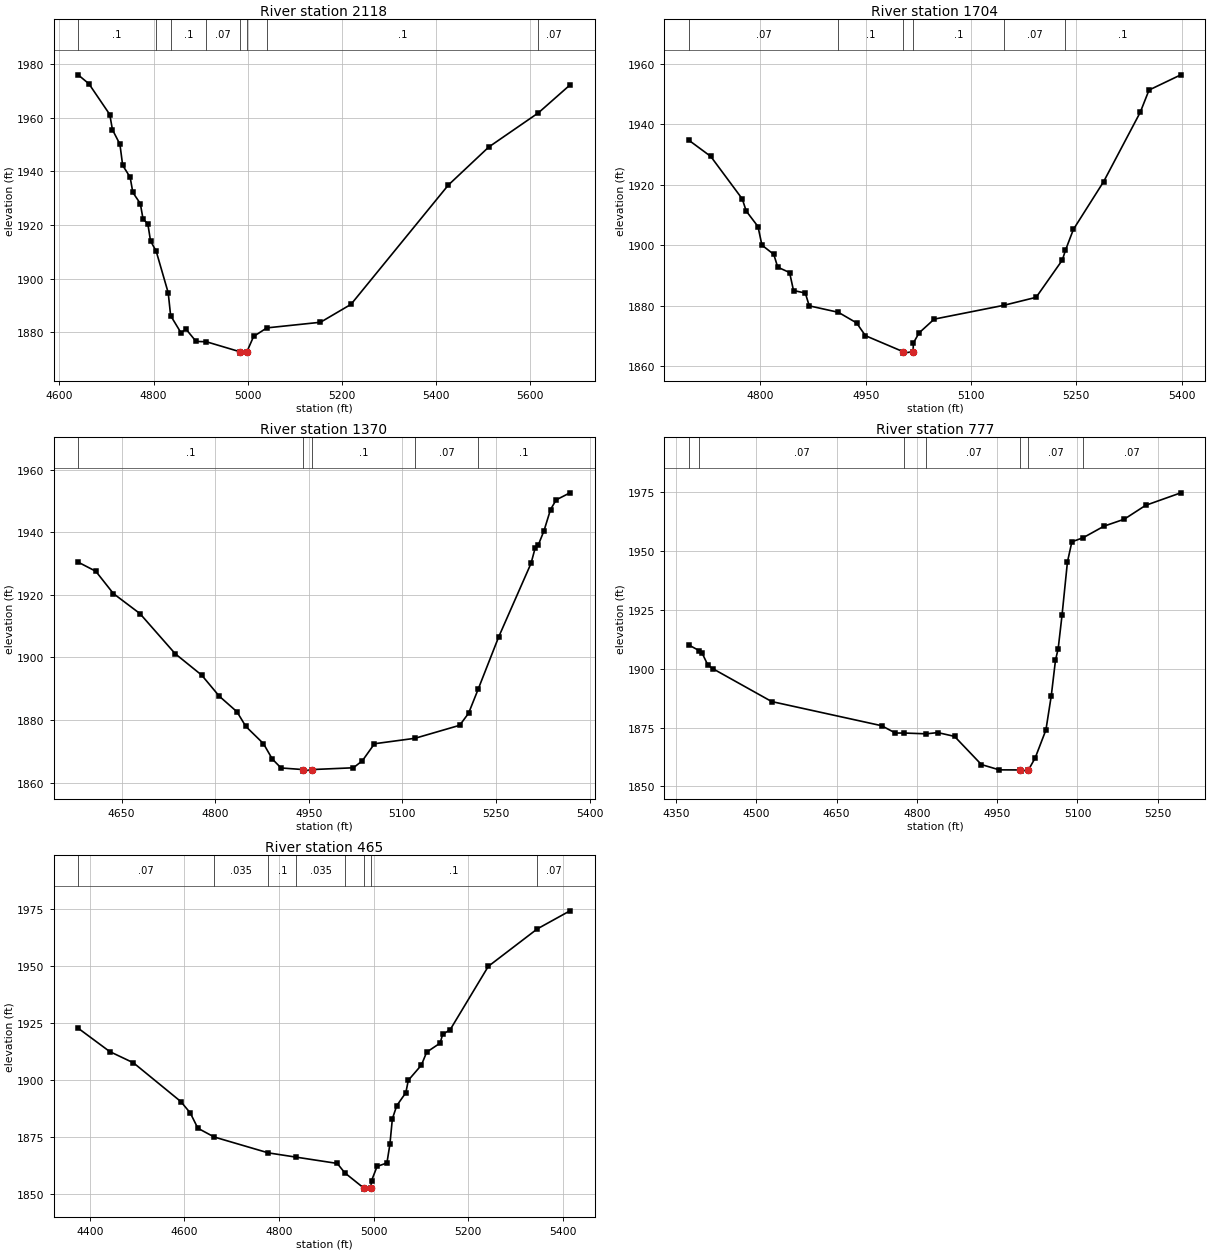
Type RM Length L Ch R = 1 ,2118    ,414,414,414
BEGIN DESCRIPTION:
Buffalo Creek 4.0
END DESCRIPTION:
XS GIS Cut Line= 3
      1845325.02     13910374.99      1845582.82     13910229.56
        1846025.       13909625.
#Sta/Elev= 30
  4639.8 1975.96  4662.7 1972.61    4707 1961.16  4712.7  1955.5  4728.6 1950.07
  4734.4 1942.22  4750.3 1937.77    4756 1932.11  4771.9 1927.95  4777.7 1922.19
  4787.9 1920.38  4793.6 1914.04  4805.7 1910.14  4831.2 1894.67  4836.3 1886.17
  4858.6 1879.69  4868.8 1881.16  4890.4 1876.54  4912.3 1876.42  4983.8 1872.68
  4984.3 1872.18  4998.3 1872.68  5012.6 1878.39  5040.7 1881.59  5154.7 1883.69
  5219.6 1890.38  5426.5 1934.88  5512.2 1949.03  5617.6 1961.77  5684.8 1972.17
#Mann= 8 ,-1 , 0
  4639.8      .1       0  4805.7     .07       0  4836.3      .1       0
  4912.3     .07       0  4983.8     .05       0  4998.3     .07       0
  5040.7      .1       0  5617.6     .07       0
Bank Sta=4983.8,4998.3
XS Rating Curve= 0 ,0
Exp/Cntr=0.3,0.1

Type RM Length L Ch R = 1 ,1704    ,334,334,334
BEGIN DESCRIPTION:
Buffalo Creek 3.0
END DESCRIPTION:
XS GIS Cut Line= 3
      1845724.97     13910425.02      1845950.82     13910313.81
      1846175.02     13909924.96
#Sta/Elev= 30
  4698.3 1934.71  4729.3 1929.39  4774.2 1915.32  4779.8 1911.32  4796.6 1906.17
  4802.2 1900.03  4819.1 1896.96  4824.7 1892.73  4841.6 1890.95  4847.2    1885
    4864 1884.17  4869.6 1879.93  4911.1 1877.79    4937 1874.29  4949.6 1870.06
  5003.1 1864.78  5003.6 1864.28  5017.6 1864.78  5017.9 1867.63  5026.1 1870.98
  5047.6 1875.53  5146.7  1880.1  5192.8 1882.75  5230.1 1895.08  5234.6 1898.34
  5245.9 1905.24    5289 1921.06  5341.1 1943.99  5353.6 1951.35  5398.9 1956.39
#Mann= 6 ,-1 , 0
  4698.3     .07       0  4911.1      .1       0  5003.1     .05       0
  5017.6      .1       0  5146.7     .07       0  5234.6      .1       0
Bank Sta=5003.1,5017.6
XS Rating Curve= 0 ,0
Exp/Cntr=0.3,0.1

Type RM Length L Ch R = 1 ,1370    ,593,593,593
BEGIN DESCRIPTION:
Buffalo Creek 2.0
END DESCRIPTION:
XS GIS Cut Line= 3
      1845975.02     13910674.98        1846275.       13910375.
      1846374.99     13910025.04
#Sta/Elev= 30
  4580.4 1930.42  4608.7 1927.51  4636.9 1920.38  4679.4 1913.99  4735.9 1901.17
  4778.4 1894.32  4806.6 1887.59  4834.9 1882.62  4849.1 1877.94  4877.4 1872.43
  4891.5 1867.53  4905.6 1864.66  4940.8 1864.15  4941.3 1863.65  4955.3 1864.15
  5021.5 1864.72  5035.8 1866.94  5055.3  1872.4  5120.2 1874.14  5191.8 1878.29
  5206.1 1882.14  5221.5 1889.84  5254.2 1906.46  5306.2 1930.04  5312.7 1934.87
  5317.9 1935.93    5327 1940.48  5337.4 1947.22  5346.5 1950.32  5368.6 1952.57
#Mann= 5 ,-1 , 0
  4580.4      .1       0  4940.8     .05       0  4955.3      .1       0
  5120.2     .07       0  5221.5      .1       0
Bank Sta=4940.8,4955.3
XS Rating Curve= 0 ,0
Exp/Cntr=0.3,0.1

Type RM Length L Ch R = 1 ,777     ,312,312,312
BEGIN DESCRIPTION:
Buffalo Creek 1.0
END DESCRIPTION:
XS GIS Cut Line= 3
       1846131.1     13910652.83      1846846.66     13910587.15
      1847037.68     13910527.45
#Sta/Elev= 30
  4374.3    1910  4393.2 1907.67  4398.3 1906.84  4409.3 1901.65  4418.4 1900.04
  4528.8 1886.03  4734.1 1875.78  4759.8 1872.67  4776.6 1872.67  4817.6 1872.33
    4839 1872.86  4870.3 1871.25  4920.5 1859.29  4953.9 1857.04  4993.4    1857
  4993.9  1856.5  5008.3    1857  5020.9 1862.06    5041 1873.97    5051 1888.46
  5058.9  1903.6  5063.9 1908.45  5071.1 1922.66  5081.2 1945.27  5089.5 1953.84
  5110.7 1955.59  5149.6 1960.49  5187.3 1963.43  5227.3 1969.32    5293 1974.63
#Mann= 7 ,-1 , 0
  4374.3      .1       0  4393.2     .07       0  4776.6    .035       0
  4817.6     .07       0  4993.4     .05       0  5008.3     .07       0
  5110.7     .07       0
Bank Sta=4993.4,5008.3
XS Rating Curve= 0 ,0
Exp/Cntr=0.3,0.1

Type RM Length L Ch R = 1 ,465     ,0,0,0
BEGIN DESCRIPTION:
Buffalo Creek 0.0
END DESCRIPTION:
XS GIS Cut Line= 4
       1846208.2     13910879.01      1846719.58     13910901.14
      1846977.87     13910826.61      1847124.19     13910612.76
#Sta/Elev= 30
  4375.5 1922.73  4442.4 1912.47  4492.4 1907.56  4592.5  1890.6  4612.5 1885.62
  4628.6  1878.9  4663.1 1875.06  4777.6  1868.1  4836.5 1866.23  4923.3 1863.48
  4939.2 1859.37  4979.2 1852.72  4979.7 1852.22  4994.1 1852.72  4995.8 1855.92
  5007.5 1862.17  5028.3 1863.68  5034.6 1871.86  5039.8 1883.01  5049.1 1888.79
  5068.3 1894.48  5073.5  1899.9  5101.2 1906.56  5112.3 1912.23  5140.8 1916.19
    5146 1919.98  5162.1 1922.09  5242.7 1949.84  5346.4 1966.26  5415.3 1974.15
#Mann= 8 ,-1 , 0
  4375.5     .07       0  4663.1    .035       0  4777.6      .1       0
  4836.5    .035       0  4939.2      .1       0  4979.2     .05       0
  4994.1      .1       0  5346.4     .07       0
Bank Sta=4979.2,4994.1
XS Rating Curve= 0 ,0
Exp/Cntr=0.3,0.1

Chan Stop Cuts=-1
Use User Specified Reach Order=0
Composite Channel Slope=5