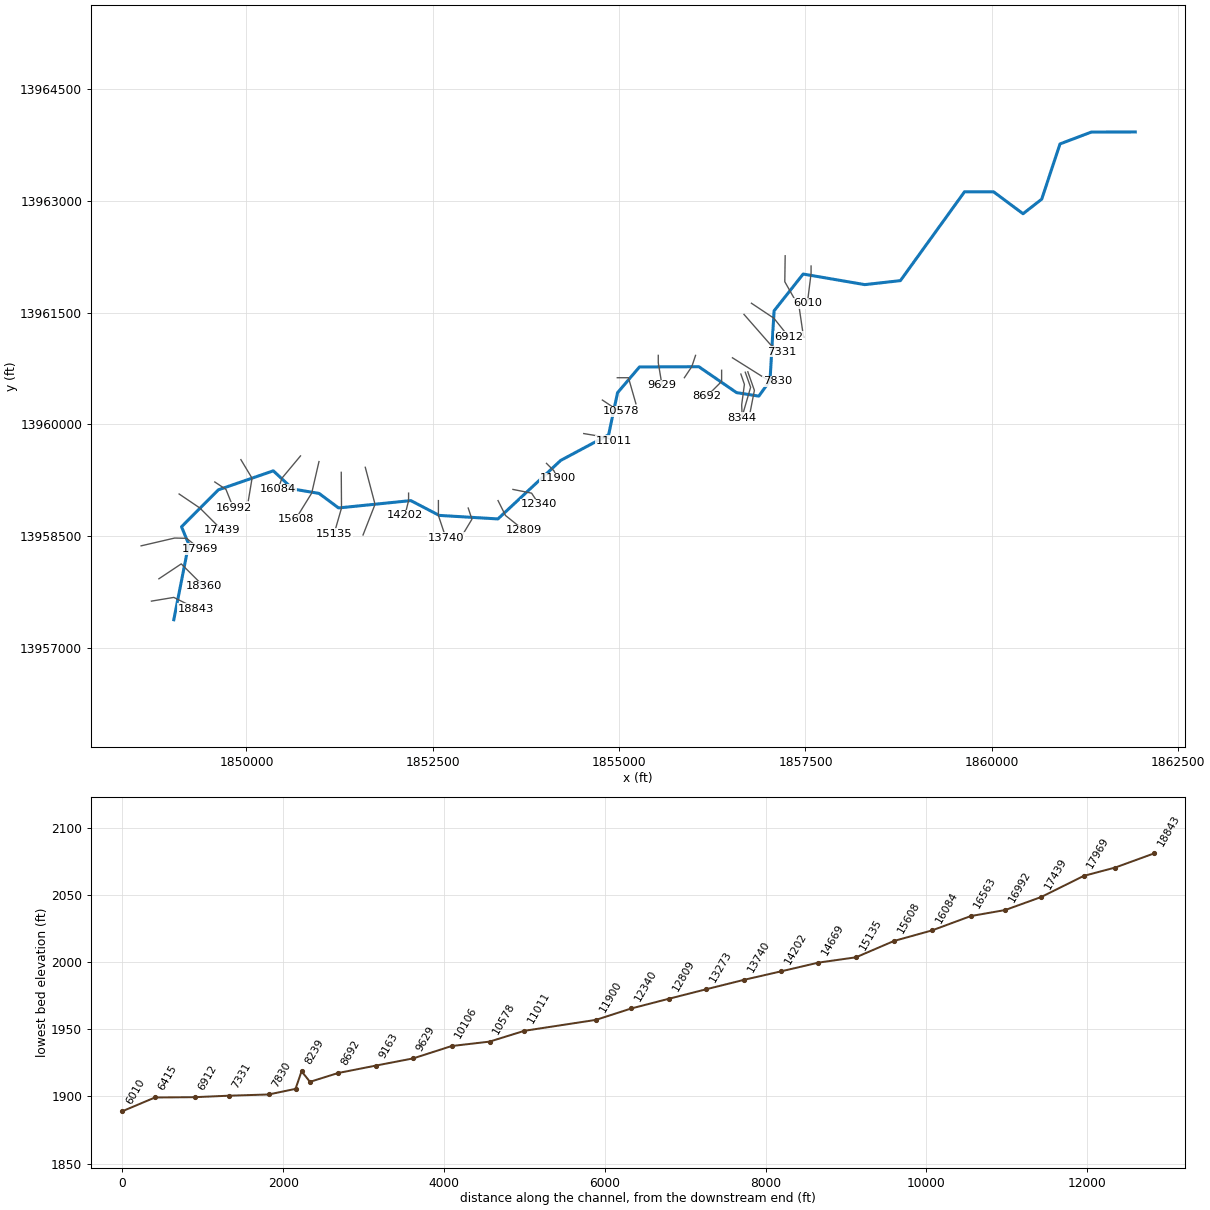
--- Byas Branch.prj (project) ---

Proj Title=Byas Branch Base Level Engineering
Current Plan=p01
Default Exp/Contr=0.3,0.1
English Units
Geom File=g01
Flow File=f01
Plan File=p01
Y Axis Title=Elevation
X Axis Title(PF)=Main Channel Distance
X Axis Title(XS)=Station
BEGIN DESCRIPTION:
Byas Branch
END DESCRIPTION:
DSS Export Rating Curves= 0
DSS Export Rating Curve Sorted= 0
DSS Export Volume Flow Curves= 0
DXF OffsetX= 0
DXF OffsetY= 0
DXF ScaleX= 1
DXF ScaleY= 10

--- Byas Branch.p01 (plan) ---

Plan Title=Multiple Run
Short Identifier=Multiple
Geom File=g01
Flow File=f01
Subcritical Flow
K Sum by GR= 0
Std Step Tol= 0.01
Critical Tol= 0.01
Num of Std Step Trials= 20
Max Error Tol= 0.3
Flow Tol Ratio= 0.001
Split Flow NTrial= 30
Split Flow Tol= 0.02
Split Flow Ratio= 0.02
Log Output Level= 0
Friction Slope Method= 1
Unsteady Friction Slope Method= 2
Unsteady Bridges Friction Slope Method= 1
Parabolic Critical Depth
Global Vel Dist=  1 , 1 , 1
Global Log Level= 0
CheckData=True
Encroach Param= -1, 0, 0, 0
BEGIN DESCRIPTION:
Multiple Run
END DESCRIPTION:

--- Byas Branch.f01 (steady flow) ---

Flow Title=Multiple
Program Version=4.10
Number of Profiles= 7
Profile Names=10-year,25-year,50-year,1pct_min,100-year,1pct_plu,500-year
River Rch & RM=Byas Branch,Reach-1         ,18843
     450     729     980     640    1277    2548    2136
River Rch & RM=Byas Branch,Reach-1         ,16563
    1468    2548    3593    2446    4881    9739    8902
River Rch & RM=Byas Branch,Reach-1         ,11011
    2197    3894    5568    3839    7659   15282   14332
River Rch & RM=Byas Branch,Reach-1         ,8344
    2512    4477    6424    4442    8863   17683   16687
River Rch & RM=Byas Branch,Reach-1         ,5061
    2737    4894    7038    4875    9726   19407   18378
River Rch & RM=Byas Branch,Reach-1         ,2292
    2861    5122    7372    5110   10195   20343   19290
Boundary for River Rch & Prof#=Byas Branch,Reach-1         , 1
Up Type= 0
Dn Type= 3
Dn Slope=0.09
Boundary for River Rch & Prof#=Byas Branch,Reach-1         , 2
Up Type= 0
Dn Type= 3
Dn Slope=0.09
Boundary for River Rch & Prof#=Byas Branch,Reach-1         , 3
Up Type= 0
Dn Type= 3
Dn Slope=0.09
Boundary for River Rch & Prof#=Byas Branch,Reach-1         , 4
Up Type= 0
Dn Type= 3
Dn Slope=0.09
Boundary for River Rch & Prof#=Byas Branch,Reach-1         , 5
Up Type= 0
Dn Type= 3
Dn Slope=0.09
Boundary for River Rch & Prof#=Byas Branch,Reach-1         , 6
Up Type= 0
Dn Type= 3
Dn Slope=0.09
Boundary for River Rch & Prof#=Byas Branch,Reach-1         , 7
Up Type= 0
Dn Type= 3
Dn Slope=0.09
DSS Import GetInterval= 0
DSS Import GetPeak= 0
DSS Import FillOption= 0

--- Byas Branch.g01 (geometry) ---

Geom Title=Existing Conditions
Program Version=4.10

River Reach=Byas Branch     ,Reach-1
Reach XY= 30
        1849025.       13957375.      1849224.98     13958390.41
      1849128.46      13958623.5      1849622.57     13959119.48
      1850359.78     13959374.76      1850622.57     13959130.52
      1850973.54     13959071.46       1851235.5     13958876.19
      1852204.97     13958974.94       1852585.5      13958776.2
      1853373.45     13958728.75      1854215.29     13959514.25
      1854858.58      13959858.2      1854978.55     13960423.53
      1855272.55     13960769.53      1856069.07     13960772.76
        1856575.       13960425.      1856873.57     13960378.01
      1857023.95     13960585.44      1857078.82     13961523.41
      1857468.79      13962017.2      1858295.03     13961875.07
       1858773.5     13961928.61      1859633.48     13963121.49
      1860023.53     13963121.46      1860418.89     13962826.79
      1860669.17      13963022.7      1860914.94     13963764.39
      1861335.44     13963923.94        1861925.       13963925.

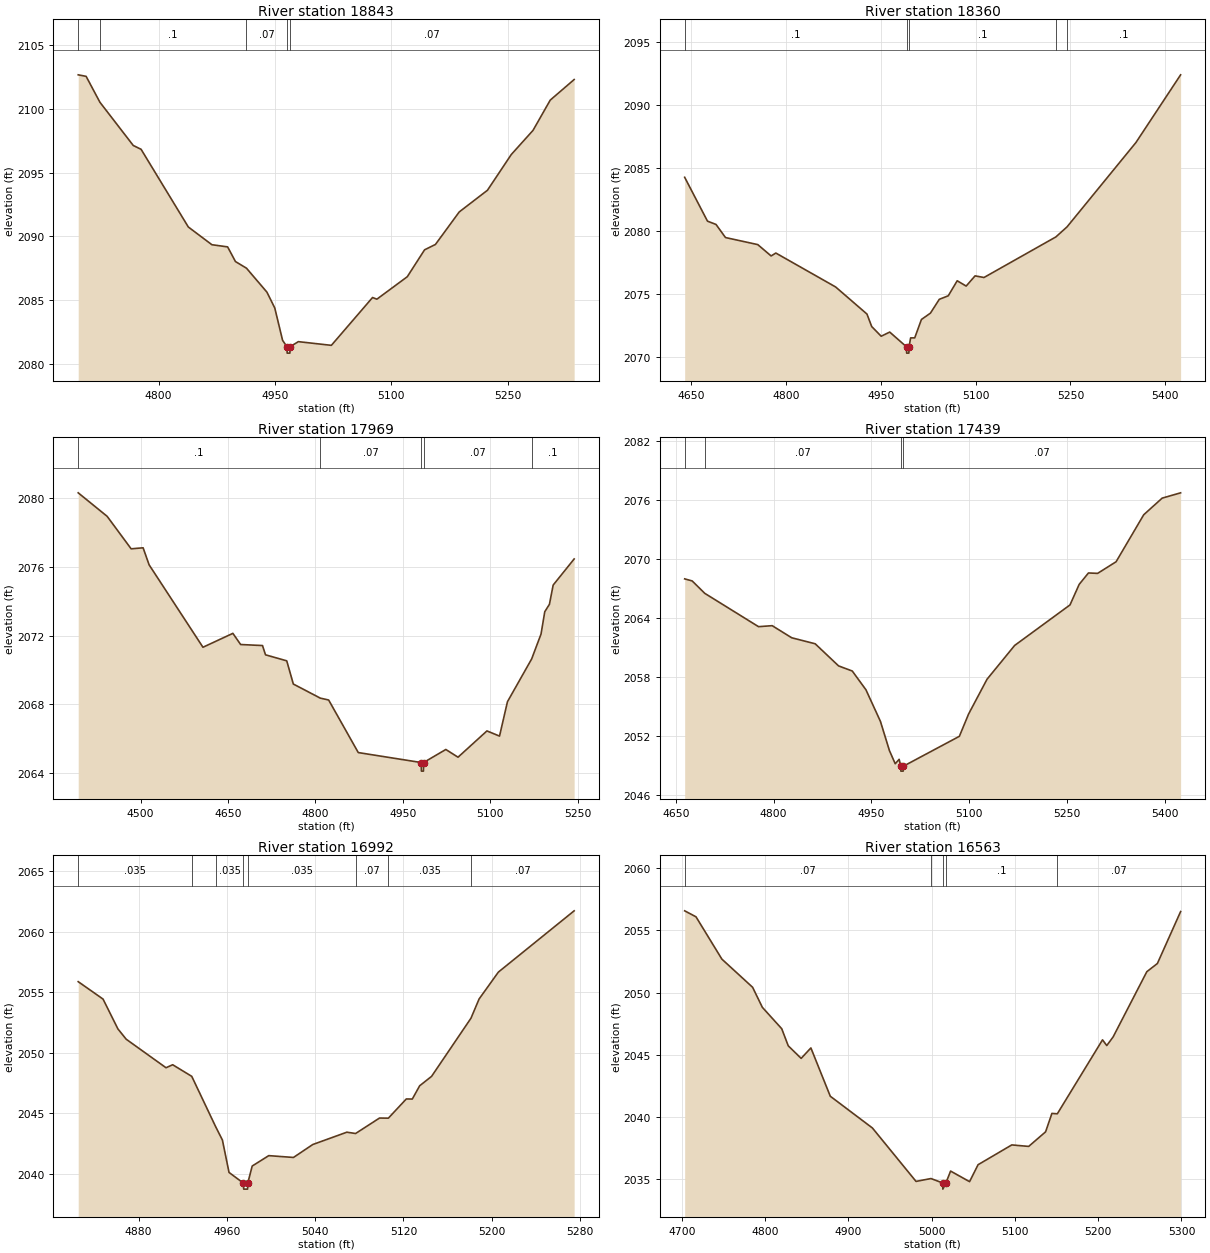
Type RM Length L Ch R = 1 ,18843   ,483,483,483
BEGIN DESCRIPTION:
Byas Branch 37.0
END DESCRIPTION:
XS GIS Cut Line= 3
      1848724.96     13957624.99        1849025.       13957675.
      1849325.01     13957524.99
#Sta/Elev= 30
  4696.3 2102.66  4706.5 2102.54  4724.3 2100.51  4767.3 2097.12  4777.4 2096.82
  4838.3 2090.73  4868.7 2089.34    4889 2089.17  4899.1 2088.02  4913.3  2087.5
  4939.7 2085.62  4949.8 2084.38  4959.9 2081.84  4965.5 2081.34  4965.8 2080.84
  4969.3 2080.84  4969.5 2081.34  4980.2 2081.74  5022.8 2081.45  5075.9  2085.2
  5081.5 2085.07  5120.7 2086.83    5143 2088.94    5157 2089.36  5187.7 2091.91
  5224.1 2093.61  5254.8 2096.41  5282.8  2098.3  5305.1 2100.68  5335.9 2102.29
#Mann= 5 ,-1 , 0
  4696.3     .07       0  4724.3      .1       0  4913.3     .07       0
  4965.5     .05       0  4969.5     .07       0
Bank Sta=4965.5,4969.5
XS Rating Curve= 0 ,0
Exp/Cntr=0.3,0.1

Type RM Length L Ch R = 1 ,18360   ,391,391,391
BEGIN DESCRIPTION:
Byas Branch 36.0
END DESCRIPTION:
XS GIS Cut Line= 3
      1848824.96     13957924.97        1849125.       13958125.
      1849425.02     13957824.98
#Sta/Elev= 30
  4639.5 2084.27  4675.6 2080.79  4689.1 2080.53  4704.1 2079.49  4755.2 2078.93
  4776.3 2078.03  4783.8 2078.26  4878.4 2075.57    4928 2073.42  4935.5 2072.43
  4950.5 2071.66    4964 2071.99  4990.6 2070.82  4990.8 2070.32  4994.3 2070.32
  4994.6 2070.82  4997.1 2071.53  5003.6 2071.53  5014.2 2072.99  5028.4 2073.49
  5042.5 2074.59  5056.7 2074.87  5070.8 2076.06    5085 2075.64  5099.1 2076.45
  5113.2 2076.32    5227 2079.54  5244.7 2080.34  5353.7 2087.03  5424.4  2092.4
#Mann= 5 ,-1 , 0
  4639.5      .1       0  4990.6     .05       0  4994.6      .1       0
    5227     .07       0  5244.7      .1       0
Bank Sta=4990.6,4994.6
XS Rating Curve= 0 ,0
Exp/Cntr=0.3,0.1

Type RM Length L Ch R = 1 ,17969   ,530,530,530
BEGIN DESCRIPTION:
Byas Branch 35.0
END DESCRIPTION:
XS GIS Cut Line= 4
      1848586.58      13958367.4      1849036.63     13958471.98
      1849195.79     13958468.37      1849374.96     13958325.03
#Sta/Elev= 30
    4393 2080.32  4442.7 2078.95  4483.8 2077.06  4504.3 2077.12  4514.6 2076.13
    4607 2071.33  4658.3 2072.14  4671.6 2071.49  4709.1 2071.43  4714.3 2070.89
  4750.7 2070.54    4762 2069.19  4808.2 2068.37  4822.6 2068.26  4873.4  2065.2
  4981.4 2064.62  4981.7 2064.12  4985.2 2064.12  4985.4 2064.62  5023.6 2065.38
  5044.5 2064.93  5094.1 2066.46  5115.7 2066.16  5129.3 2068.16  5170.8 2070.65
  5186.9  2072.1  5193.3  2073.4  5201.3 2073.83  5207.7 2074.95  5243.7 2076.47
#Mann= 5 ,-1 , 0
    4393      .1       0  4808.2     .07       0  4981.4     .05       0
  4985.4     .07       0  5170.8      .1       0
Bank Sta=4981.4,4985.4
XS Rating Curve= 0 ,0
Exp/Cntr=0.3,0.1

Type RM Length L Ch R = 1 ,17439   ,447,447,447
BEGIN DESCRIPTION:
Byas Branch 34.0
END DESCRIPTION:
XS GIS Cut Line= 3
      1849096.34     13959063.64        1849375.       13958875.
      1849675.02     13958574.98
#Sta/Elev= 30
  4663.5 2067.94    4675 2067.73  4694.3 2066.47  4776.8 2063.08  4797.8 2063.18
  4827.7 2061.95  4863.7 2061.34  4899.6 2059.09  4920.6 2058.57  4941.6 2056.66
  4963.8 2053.45  4977.6 2050.48  4986.5 2049.14  4992.5 2049.59    4995 2048.89
  4995.2 2048.39  4998.7 2048.39    4999 2048.89  5084.9 2051.93    5099 2054.19
  5127.3 2057.73  5169.7 2061.17  5254.6 2065.29  5268.7 2067.38  5282.9 2068.54
    5297  2068.5  5325.3 2069.68  5367.7 2074.46    5396 2076.15  5424.3 2076.69
#Mann= 4 ,-1 , 0
  4663.5      .1       0  4694.3     .07       0    4995     .05       0
    4999     .07       0
Bank Sta=4995,4999
XS Rating Curve= 0 ,0
Exp/Cntr=0.3,0.1

Type RM Length L Ch R = 1 ,16992   ,429,429,429
BEGIN DESCRIPTION:
Byas Branch 33.0
END DESCRIPTION:
XS GIS Cut Line= 3
      1849575.03     13959224.98        1849725.       13959125.
        1849825.       13958875.
#Sta/Elev= 30
  4825.2 2055.88  4847.7 2054.44  4861.2 2051.97  4868.7 2051.12  4904.8 2048.76
  4910.8 2049.01  4928.1 2048.05  4949.8 2043.88  4955.9 2042.78  4961.9  2040.1
  4974.9 2039.22  4975.2 2038.72  4978.7 2038.72  4978.9 2039.22  4982.9 2040.63
  4997.9 2041.49  5020.3 2041.34  5037.8 2042.41  5068.7 2043.43  5076.6 2043.32
  5098.3  2044.6  5106.3 2044.59  5122.6 2046.18    5128 2046.17  5134.7 2047.27
  5145.5 2048.05  5181.2 2052.86  5188.5 2054.44    5206 2056.67  5274.7 2061.74
#Mann= 8 ,-1 , 0
  4825.2    .035       0  4928.1     .07       0  4949.8    .035       0
  4974.9    .035       0  4978.9    .035       0  5076.6     .07       0
  5106.3    .035       0  5181.2     .07       0
Bank Sta=4974.9,4978.9
XS Rating Curve= 0 ,0
Exp/Cntr=0.3,0.1

Type RM Length L Ch R = 1 ,16563   ,479,479,479
BEGIN DESCRIPTION:
Byas Branch 32.0
END DESCRIPTION:
XS GIS Cut Line= 3
        1849925.       13959525.        1850075.       13959275.
        1850025.     13958974.99
#Sta/Elev= 30
  4703.3 2056.57  4716.9 2056.09    4748 2052.69  4784.9 2050.43  4796.6 2048.82
  4819.9  2047.1  4827.7 2045.73  4843.2 2044.72  4854.9 2045.56  4878.2 2041.68
  4928.8 2039.13  4981.2 2034.84  4999.1 2035.07  5013.1 2034.72  5013.4 2034.22
  5017.1 2034.72  5022.7 2035.67  5045.5 2034.82  5055.7 2036.18  5096.2 2037.77
  5116.5 2037.65  5136.8 2038.82  5144.4  2040.3  5150.9 2040.27  5205.2 2046.21
  5210.3 2045.75  5217.9 2046.44  5258.4 2051.68  5271.1 2052.34    5299 2056.51
#Mann= 5 ,-1 , 0
  4703.3     .07       0  4999.1      .1       0  5013.1     .05       0
  5017.1      .1       0  5150.9     .07       0
Bank Sta=5013.1,5017.1
XS Rating Curve= 0 ,0
Exp/Cntr=0.3,0.1

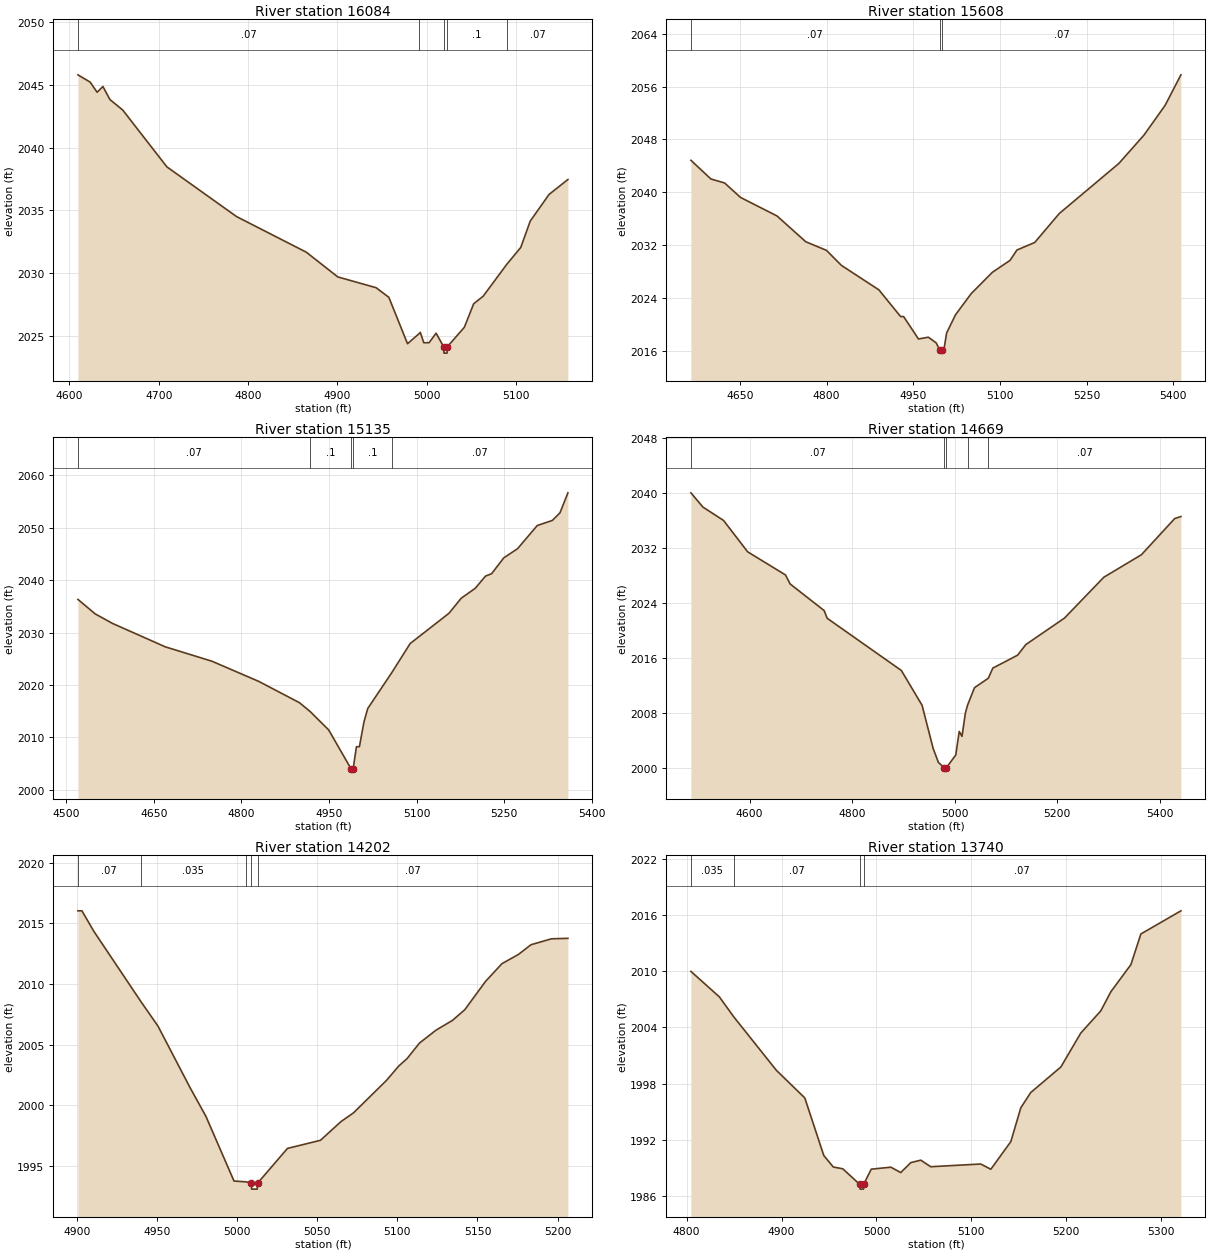
Type RM Length L Ch R = 1 ,16084   ,476,476,476
BEGIN DESCRIPTION:
Byas Branch 31.0
END DESCRIPTION:
XS GIS Cut Line= 3
      1850725.02     13959575.02        1850475.       13959275.
      1850424.99     13959124.96
#Sta/Elev= 30
  4609.5  2045.8  4623.2 2045.22    4631 2044.41  4637.5 2044.87  4645.3 2043.83
  4659.6    2043  4709.1 2038.46  4787.2 2034.49  4865.3 2031.65  4900.5 2029.68
  4943.4 2028.82  4957.7 2028.05  4978.6 2024.35  4991.5 2025.15  4992.9 2025.26
  4996.8 2024.43  5002.7 2024.43  5010.6 2025.19  5019.1  2024.1  5019.4  2023.6
  5022.9  2023.6  5023.1  2024.1  5042.2 2025.66  5052.7 2027.54  5063.3 2028.14
  5089.7 2030.68  5105.4 2032.03    5116 2034.13  5137.1 2036.26  5158.2 2037.45
#Mann= 5 ,-1 , 0
  4609.5     .07       0  4991.5      .1       0  5019.1     .05       0
  5023.1      .1       0  5089.7     .07       0
Bank Sta=5019.1,5023.1
XS Rating Curve= 0 ,0
Exp/Cntr=0.3,0.1

Type RM Length L Ch R = 1 ,15608   ,473,473,473
BEGIN DESCRIPTION:
Byas Branch 30.0
END DESCRIPTION:
XS GIS Cut Line= 3
      1850972.68      13959498.7        1850875.       13959075.
      1850657.56     13958723.66
#Sta/Elev= 30
  4565.2 2044.85  4599.8 2042.02  4623.5 2041.42  4651.1 2039.23  4714.2 2036.43
    4764 2032.53  4799.8 2031.23  4825.6 2028.96  4890.5 2025.26  4928.1 2021.22
  4933.3 2021.22    4959 2017.83  4976.1  2018.1  4989.8 2017.23  4995.5 2016.19
  4995.7 2015.69  4999.5 2016.19    5003 2016.19  5007.7 2018.73  5023.1 2021.49
  5050.2 2024.68  5086.9 2027.91  5117.6 2029.72  5129.4 2031.28  5160.2 2032.42
  5202.7  2036.8  5305.8 2044.37  5349.2 2048.65  5385.9 2053.16  5413.2 2057.77
#Mann= 3 ,-1 , 0
  4565.2     .07       0  4995.5     .05       0  4999.5     .07       0
Bank Sta=4995.5,4999.5
XS Rating Curve= 0 ,0
Exp/Cntr=0.3,0.1

Type RM Length L Ch R = 1 ,15135   ,466,466,466
BEGIN DESCRIPTION:
Byas Branch 29.0
END DESCRIPTION:
XS GIS Cut Line= 3
      1851271.67     13959354.52        1851275.       13958875.
      1851175.53     13958529.36
#Sta/Elev= 30
    4520 2036.32  4549.5 2033.56  4579.5 2031.72  4669.5 2027.27  4749.5 2024.52
  4829.5 2020.68  4899.5  2016.6  4917.9  2014.9  4949.5  2011.4  4987.5 2004.04
  4987.8 2003.54  4991.3 2003.54  4991.5 2004.04    4997  2008.2  5002.1  2008.2
  5009.9 2012.93  5016.4  2015.5  5057.1 2022.26    5089 2027.89  5155.6 2033.68
  5176.4 2036.54  5200.4 2038.43  5218.1 2040.77  5228.5 2041.22  5249.3 2044.24
    5273    2046  5306.7 2050.42  5332.5 2051.39  5345.6 2052.84  5359.2 2056.66
#Mann= 5 ,-1 , 0
    4520     .07       0  4917.9      .1       0  4987.5     .05       0
  4991.5      .1       0  5057.1     .07       0
Bank Sta=4987.5,4991.5
XS Rating Curve= 0 ,0
Exp/Cntr=0.3,0.1

Type RM Length L Ch R = 1 ,14669   ,467,467,467
BEGIN DESCRIPTION:
Byas Branch 28.0
END DESCRIPTION:
XS GIS Cut Line= 3
      1851593.87     13959422.07        1851725.       13958925.
      1851563.83     13958513.29
#Sta/Elev= 30
  4485.5 2040.09  4508.9 2038.02  4549.2 2036.07  4596.2 2031.51  4670.1 2028.14
    4679 2026.84  4745.5 2022.96  4751.4 2021.84  4896.2 2014.24  4936.6 2009.18
  4958.2  2002.9  4968.5 2000.86    4980  2000.1  4980.3  1999.6    4984  2000.1
  5002.3 2001.94  5009.1 2005.37  5014.5 2004.66  5021.1 2008.05  5025.5 2009.23
  5038.9 2011.74  5065.9 2013.12  5074.7 2014.59    5123 2016.47  5139.2 2018.02
  5214.4 2021.86  5291.3 2027.81  5364.6 2031.08  5429.6 2036.35  5441.7 2036.64
#Mann= 5 ,-1 , 0
  4485.5     .07       0    4980     .05       0    4984     .07       0
  5025.5      .1       0  5065.9     .07       0
Bank Sta=4980,4984
XS Rating Curve= 0 ,0
Exp/Cntr=0.3,0.1

Type RM Length L Ch R = 1 ,14202   ,462,462,462
BEGIN DESCRIPTION:
Byas Branch 27.0
END DESCRIPTION:
XS GIS Cut Line= 3
        1852175.     13959074.99        1852175.       13958975.
      1852125.01     13958775.05
#Sta/Elev= 30
  4900.4 2016.04  4902.9 2016.04  4910.4 2014.34  4939.6 2008.58  4950.4 2006.53
  4970.4 2001.46  4980.4 1999.07  4997.9 1993.74  5005.4 1993.67  5008.7 1993.57
  5008.9 1993.07  5012.4 1993.07  5012.7 1993.57  5031.3 1996.43  5051.9  1997.1
  5064.8 1998.65  5072.5 1999.36  5093.2 2002.05  5100.9 2003.24    5106 2003.84
  5113.8 2005.13  5124.1 2006.19  5134.4    2007  5142.1 2007.88    5155 2010.21
  5165.3 2011.68  5175.6 2012.44  5183.4 2013.24  5196.2 2013.73  5206.5 2013.77
#Mann= 5 ,-1 , 0
  4900.4     .07       0  4939.6    .035       0  5005.4     .07       0
  5008.7    .035       0  5012.7     .07       0
Bank Sta=5008.7,5012.7
XS Rating Curve= 0 ,0
Exp/Cntr=0.3,0.1

Type RM Length L Ch R = 1 ,13740   ,467,467,467
BEGIN DESCRIPTION:
Byas Branch 26.0
END DESCRIPTION:
XS GIS Cut Line= 3
        1852575.     13958975.03        1852575.       13958775.
      1852675.01     13958474.96
#Sta/Elev= 30
  4804.5 2009.97  4834.5 2007.25  4849.5 2005.14  4894.5 1999.42  4924.5 1996.47
  4944.5 1990.33  4954.5  1989.1  4964.5 1988.91  4982.5 1987.24  4982.8 1986.74
  4986.3 1986.74  4986.5 1987.24  4994.5 1988.87  5015.1 1989.08  5025.6 1988.51
  5036.2 1989.57  5046.7 1989.83  5057.2 1989.13  5109.9 1989.42  5120.5 1988.86
  5141.6 1991.81  5152.1 1995.42  5162.6 1997.05  5194.3 1999.77  5215.3 2003.39
  5236.4 2005.76    5247  2007.8  5268.1 2010.69  5278.6 2013.96  5320.8 2016.43
#Mann= 4 ,-1 , 0
  4804.5    .035       0  4849.5     .07       0  4982.5     .05       0
  4986.5     .07       0
Bank Sta=4982.5,4986.5
XS Rating Curve= 0 ,0
Exp/Cntr=0.3,0.1

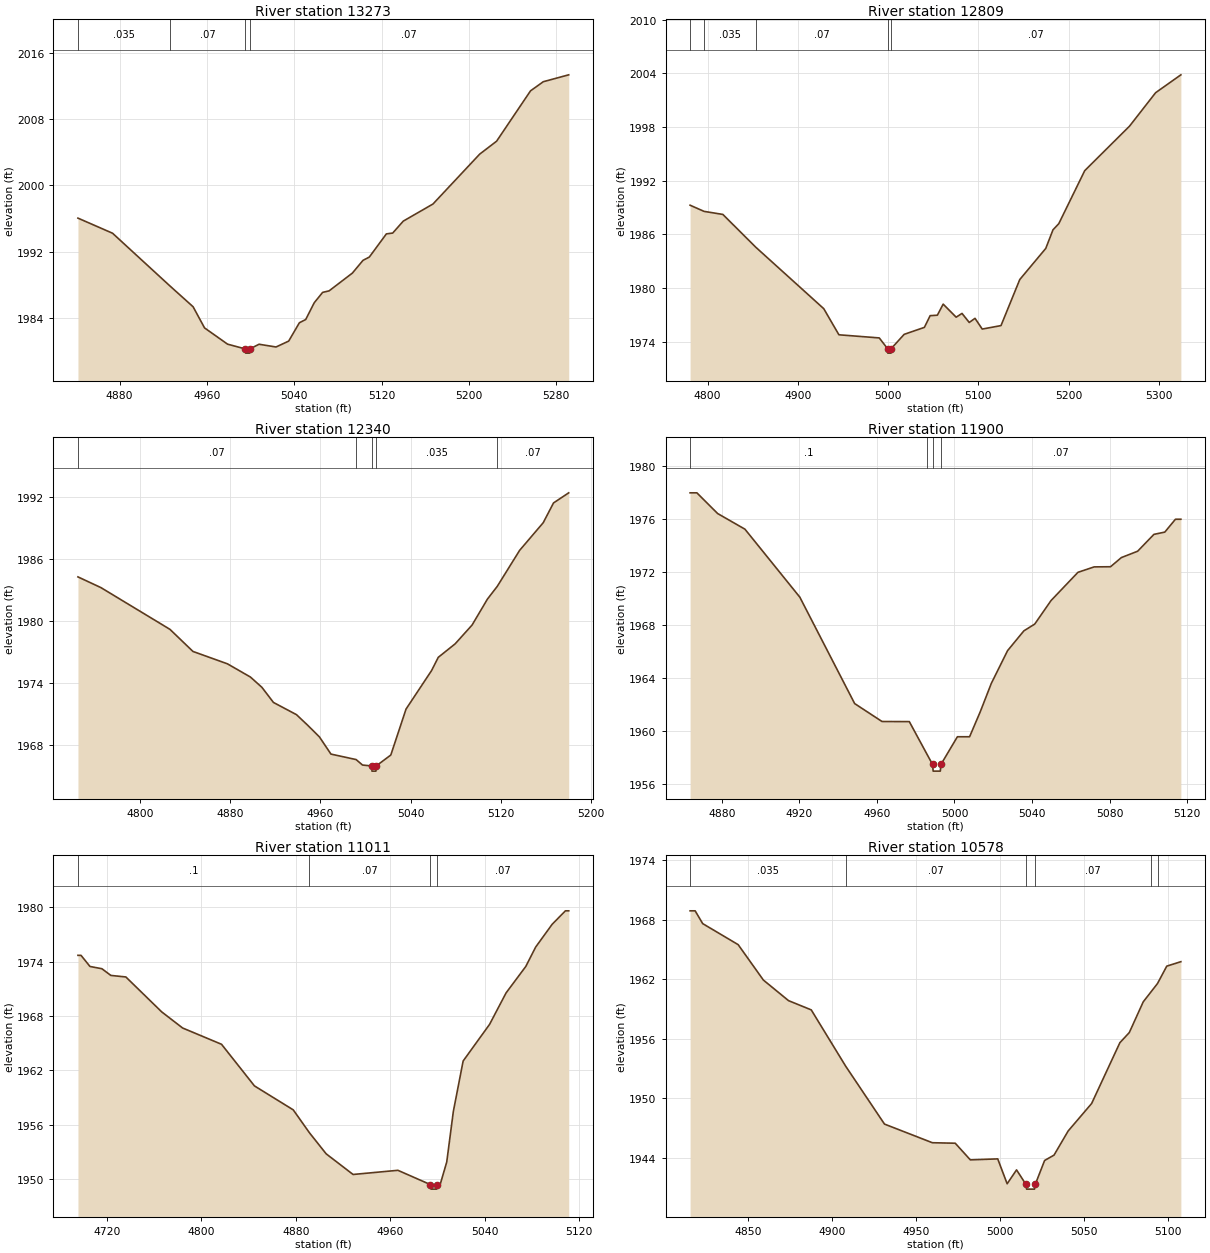
Type RM Length L Ch R = 1 ,13273   ,464,464,464
BEGIN DESCRIPTION:
Byas Branch 25.0
END DESCRIPTION:
XS GIS Cut Line= 3
      1852974.98     13958875.05        1853025.       13958725.
      1852875.01     13958475.01
#Sta/Elev= 30
  4841.8 1996.05  4873.5 1994.23  4925.8 1987.91  4947.3 1985.37  4957.8 1982.82
  4978.9 1980.86  4995.3 1980.28  4995.6 1979.78  4999.1 1979.78  4999.3 1980.28
  5007.7 1980.85  5023.3 1980.52  5034.9 1981.23  5044.7 1983.44  5050.5 1983.83
  5058.3 1985.85    5066  1987.1  5071.9 1987.28  5093.3 1989.43    5103 1990.96
  5108.8 1991.36  5124.4 1994.15  5130.2 1994.25  5139.9 1995.69  5167.1 1997.75
  5209.9 2003.76  5225.4 2005.32  5256.5 2011.39  5268.2 2012.49  5291.5 2013.32
#Mann= 4 ,-1 , 0
  4841.8    .035       0  4925.8     .07       0  4995.3     .05       0
  4999.3     .07       0
Bank Sta=4995.3,4999.3
XS Rating Curve= 0 ,0
Exp/Cntr=0.3,0.1

Type RM Length L Ch R = 1 ,12809   ,469,469,469
BEGIN DESCRIPTION:
Byas Branch 24.0
END DESCRIPTION:
XS GIS Cut Line= 3
        1853375.     13958975.01        1853475.       13958775.
      1853725.02     13958574.98
#Sta/Elev= 30
  4780.7 1989.26  4796.2 1988.57    4817 1988.23  4853.4 1984.57  4928.8 1977.69
  4945.6 1974.77  4990.3 1974.42  4999.5 1973.22  4999.8 1972.72  5003.3 1972.72
  5003.5 1973.22  5017.9 1974.82  5040.3  1975.6  5046.7 1976.91  5054.7 1976.96
  5061.1  1978.2  5075.5 1976.74    5082 1977.16    5090 1976.15  5096.4 1976.61
  5104.4 1975.41  5125.2  1975.8    5146 1980.95  5174.8 1984.43  5182.8 1986.51
  5189.2 1987.19    5218 1993.13  5267.6  1998.1  5296.5 2001.84  5324.5 2003.84
#Mann= 5 ,-1 , 0
  4780.7     .07       0  4796.2    .035       0  4853.4     .07       0
  4999.5     .05       0  5003.5     .07       0
Bank Sta=4999.5,5003.5
XS Rating Curve= 0 ,0
Exp/Cntr=0.3,0.1

Type RM Length L Ch R = 1 ,12340   ,440,440,440
BEGIN DESCRIPTION:
Byas Branch 23.0
END DESCRIPTION:
XS GIS Cut Line= 3
      1853574.96     13959125.01        1853825.       13959075.
      1853925.02     13958924.98
#Sta/Elev= 30
    4745 1984.28  4765.4 1983.24  4826.6  1979.2    4847 1977.06  4877.6 1975.86
    4898 1974.58  4908.2 1973.58  4918.4 1972.12  4938.8 1970.94    4949 1969.89
  4959.2 1968.78  4969.4 1967.12  4991.7 1966.59  4997.4 1966.06  5005.5 1965.97
  5005.8 1965.47  5009.3 1965.47  5009.5 1965.97  5022.5 1967.03    5036 1971.48
  5058.6  1975.2  5064.6 1976.49  5079.6  1977.8  5094.6 1979.62  5108.2 1982.13
  5116.9 1983.36  5136.7 1986.84  5157.7 1989.53  5166.8 1991.44  5180.3 1992.42
#Mann= 5 ,-1 , 0
    4745     .07       0  4991.7    .035       0  5005.5    .035       0
  5009.5    .035       0  5116.9     .07       0
Bank Sta=5005.5,5009.5
XS Rating Curve= 0 ,0
Exp/Cntr=0.3,0.1

Type RM Length L Ch R = 1 ,11900   ,889,889,889
BEGIN DESCRIPTION:
Byas Branch 22.0
END DESCRIPTION:
XS GIS Cut Line= 3
      1854024.99     13959475.01        1854125.       13959375.
      1854174.98     13959275.03
#Sta/Elev= 30
  4863.6 1977.95  4867.1 1977.95  4877.8 1976.39  4891.9 1975.21  4920.2 1970.09
  4948.5 1962.07  4962.6 1960.72  4976.7 1960.71  4985.9 1958.23  4988.7 1957.48
    4989 1956.98  4992.7 1956.98    4993 1957.48  5001.5 1959.57  5007.8 1959.57
  5013.4 1961.49    5019 1963.59  5027.4 1966.06  5035.8 1967.55  5041.4 1968.06
  5049.8 1969.83  5063.7 1971.96  5072.1 1972.37  5080.5 1972.38  5086.1 1973.07
  5094.5 1973.55  5102.9 1974.82  5108.5 1974.99    5114 1975.96  5116.8 1975.96
#Mann= 4 ,-1 , 0
  4863.6      .1       0  4985.9     .07       0  4988.7     .05       0
    4993     .07       0
Bank Sta=4988.7,4993
XS Rating Curve= 0 ,0
Exp/Cntr=0.3,0.1

Type RM Length L Ch R = 1 ,11011   ,433,433,433
BEGIN DESCRIPTION:
Byas Branch 21.0
END DESCRIPTION:
XS GIS Cut Line= 3
      1854524.96     13959875.01        1854825.       13959825.
      1854925.02     13959774.99
#Sta/Elev= 30
  4695.3  1974.7  4697.9  1974.7  4705.5 1973.47  4715.6 1973.22  4723.2 1972.48
  4735.9 1972.31  4766.3 1968.45    4784 1966.67    4817 1964.87  4844.9 1960.27
  4877.8 1957.62  4891.4 1955.11  4905.7 1952.76  4928.5 1950.48  4966.5 1950.94
  4994.1 1949.36  4994.6 1948.86  4999.3 1948.86  4999.7 1949.36  5002.3 1949.36
  5007.9 1951.86  5013.5 1957.45  5021.8 1963.02  5044.2 1967.07  5058.2 1970.55
  5074.9 1973.47  5083.3 1975.62  5097.3 1978.14  5108.5 1979.62  5111.3 1979.62
#Mann= 4 ,-1 , 0
  4695.3      .1       0  4891.4     .07       0  4994.1     .05       0
  4999.7     .07       0
Bank Sta=4994.1,4999.7
XS Rating Curve= 0 ,0
Exp/Cntr=0.3,0.1

Type RM Length L Ch R = 1 ,10578   ,472,472,472
BEGIN DESCRIPTION:
Byas Branch 20.0
END DESCRIPTION:
XS GIS Cut Line= 3
      1854774.98     13960325.01        1854925.       13960225.
        1855025.       13960175.
#Sta/Elev= 30
  4815.5 1968.89  4818.5 1968.89    4823  1967.6  4844.1 1965.48  4859.1 1961.91
  4874.1 1959.83  4887.6  1958.9  4908.1 1953.22  4931.2 1947.38  4959.7  1945.5
  4973.3 1945.45  4982.3 1943.77  4998.6 1943.87  5004.2 1941.36  5009.8 1942.76
  5015.3 1941.32  5015.8 1940.82  5020.5 1940.82    5021 1941.32  5026.5 1943.71
  5032.1 1944.25  5040.5 1946.68  5054.5 1949.46  5071.3 1955.59  5076.9 1956.61
  5085.2 1959.71  5089.8 1960.71  5093.7 1961.56  5099.2 1963.31  5107.6 1963.76
#Mann= 6 ,-1 , 0
  4815.5    .035       0  4908.1     .07       0  5015.3     .05       0
    5021     .07       0  5089.8    .035       0  5093.7     .07       0
Bank Sta=5015.3,5021
XS Rating Curve= 0 ,0
Exp/Cntr=0.3,0.1

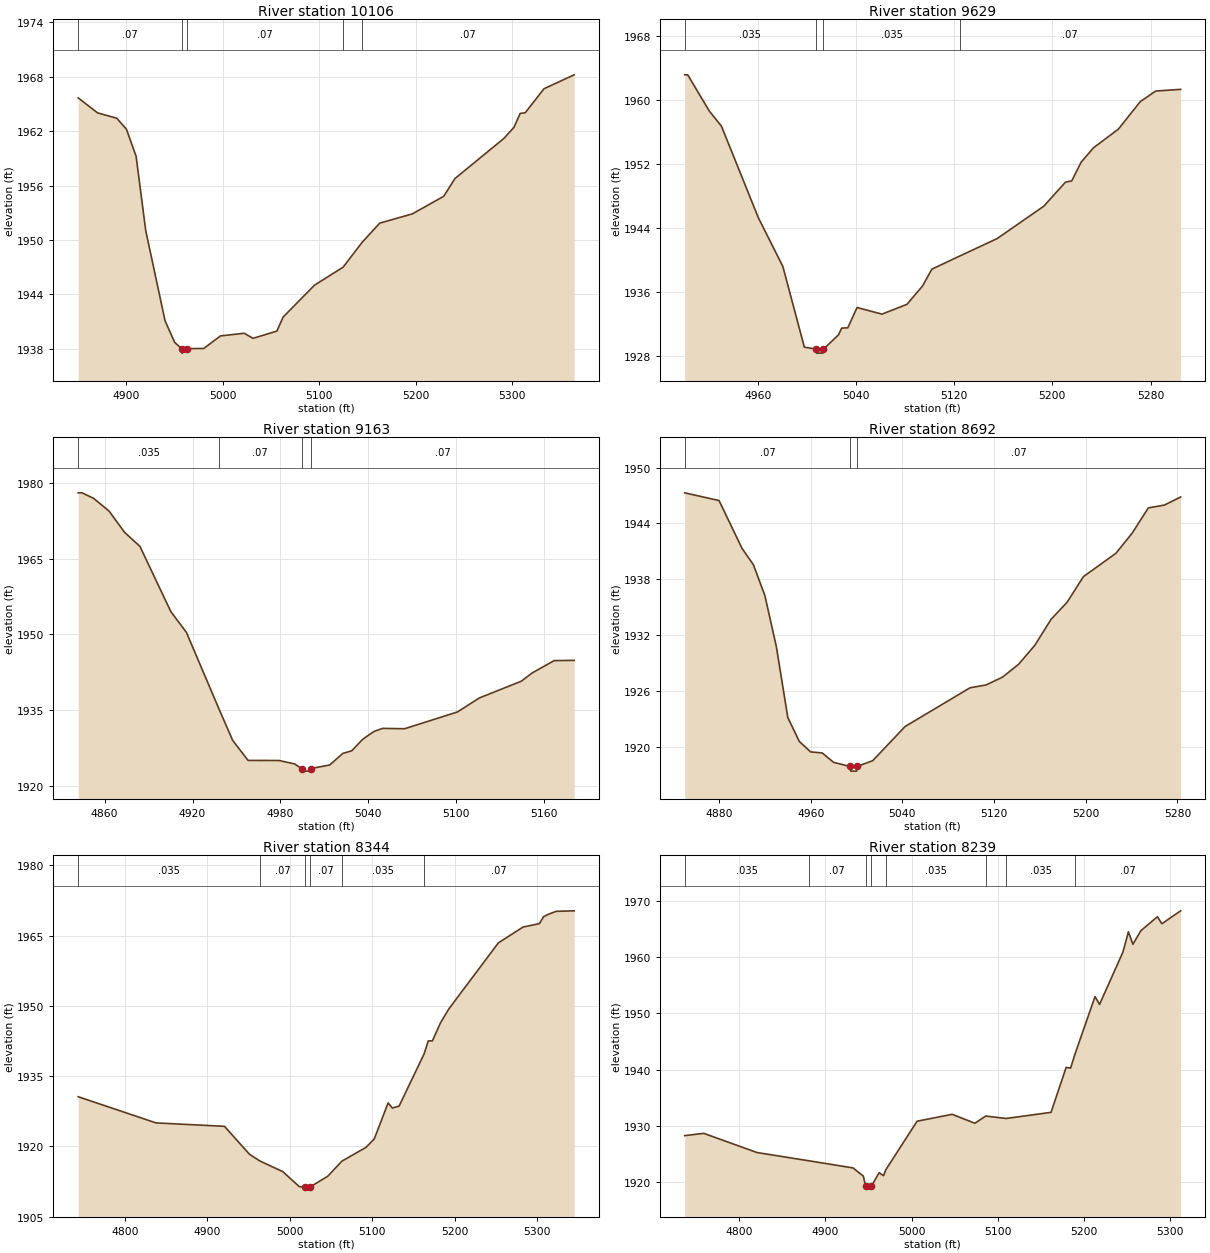
Type RM Length L Ch R = 1 ,10106   ,477,477,477
BEGIN DESCRIPTION:
Byas Branch 19.0
END DESCRIPTION:
XS GIS Cut Line= 3
        1854975.       13960625.        1855125.       13960625.
        1855225.     13960275.01
#Sta/Elev= 30
  4850.3 1965.67  4870.3 1964.02  4890.3 1963.42  4900.3 1962.21  4910.3 1959.23
  4920.3 1951.03  4940.3  1941.1  4950.3 1938.71  4957.5 1938.03  4957.9 1937.53
  4963.2 1938.03  4980.3 1938.04  4997.8 1939.43  5022.4 1939.72  5031.5 1939.16
  5056.2 1939.96  5062.7 1941.51  5095.2 1945.02  5124.9 1947.01  5144.6 1949.75
  5162.8 1951.86  5196.6 1952.88  5229.1 1954.82  5240.8 1956.78  5291.5  1961.2
  5301.9 1962.42  5308.4 1963.96  5313.6 1964.03  5333.1 1966.68  5364.3 1968.21
#Mann= 5 ,-1 , 0
  4850.3     .07       0  4957.5     .05       0  4963.2     .07       0
  5124.9    .035       0  5144.6     .07       0
Bank Sta=4957.5,4963.2
XS Rating Curve= 0 ,0
Exp/Cntr=0.3,0.1

Type RM Length L Ch R = 1 ,9629    ,466,466,466
BEGIN DESCRIPTION:
Byas Branch 18.0
END DESCRIPTION:
XS GIS Cut Line= 3
        1855525.     13960924.98        1855525.       13960825.
        1855575.     13960525.02
#Sta/Elev= 30
  4900.4  1963.2  4902.9  1963.2  4920.4 1958.68  4930.4 1956.76  4960.4 1945.32
  4980.4 1939.21  4997.9 1929.11  5007.5 1928.86    5008 1928.36    5013 1928.36
  5013.5 1928.86  5025.7 1930.64  5028.3 1931.49  5033.3 1931.53  5040.9 1934.07
  5061.2 1933.24  5081.5 1934.47  5094.2 1936.76  5101.8 1938.87  5124.6 1940.52
    5155  1942.7    5193 1946.75  5210.7 1949.77  5215.8 1949.92  5223.4 1952.25
  5233.6 1954.08  5253.8  1956.4  5271.6 1959.84  5284.2 1961.17  5304.5 1961.38
#Mann= 4 ,-1 , 0
  4900.4    .035       0  5007.5    .035       0  5013.5    .035       0
  5124.6     .07       0
Bank Sta=5007.5,5013.5
XS Rating Curve= 0 ,0
Exp/Cntr=0.3,0.1

Type RM Length L Ch R = 1 ,9163    ,471,471,471
BEGIN DESCRIPTION:
Byas Branch 17.0
END DESCRIPTION:
XS GIS Cut Line= 3
      1856024.99     13960924.98        1855975.       13960775.
      1855874.98     13960624.97
#Sta/Elev= 30
    4842 1977.99  4844.6 1977.99  4852.5  1976.9  4863.1 1974.37  4873.6 1970.19
  4884.1 1967.41  4905.2 1954.51  4915.8 1950.42    4938  1935.3  4947.4 1929.05
  4957.9 1925.09    4979 1925.07  4989.6  1924.4  4994.5 1923.47    4995 1922.97
    5000 1922.97  5000.5 1923.47  5013.6 1924.18  5022.6 1926.48  5028.6 1926.98
  5036.1 1929.26  5043.7  1930.8  5049.7 1931.42  5064.7 1931.35  5100.7 1934.66
  5115.8 1937.45  5144.3 1940.74  5151.8 1942.39  5166.8 1944.82  5180.4 1944.87
#Mann= 4 ,-1 , 0
    4842    .035       0    4938     .07       0  4994.5     .05       0
  5000.5     .07       0
Bank Sta=4994.5,5000.5
XS Rating Curve= 0 ,0
Exp/Cntr=0.3,0.1

Type RM Length L Ch R = 1 ,8692    ,348,348,348
BEGIN DESCRIPTION:
Byas Branch 16.0
END DESCRIPTION:
XS GIS Cut Line= 3
        1856375.       13960725.        1856375.       13960575.
      1856175.03     13960375.03
#Sta/Elev= 30
    4850 1947.29    4880 1946.46    4900 1941.34    4910 1939.57    4920 1936.26
    4930 1930.79    4940 1923.18    4950 1920.62    4960 1919.49    4970 1919.38
    4980 1918.37  4994.4 1917.93  4994.9 1917.43    5000 1917.43  5000.5 1917.93
  5014.1 1918.55  5042.4 1922.22    5099 1926.37  5113.1 1926.68  5127.3 1927.51
  5141.4 1928.89  5155.6 1930.94  5169.7 1933.71  5183.8 1935.56    5198  1938.3
  5226.3  1940.8  5240.4 1942.94  5254.6 1945.67  5268.7 1945.98  5282.8 1946.84
#Mann= 3 ,-1 , 0
    4850     .07       0  4994.4     .05       0  5000.5     .07       0
Bank Sta=4994.4,5000.5
XS Rating Curve= 0 ,0
Exp/Cntr=0.3,0.1

Type RM Length L Ch R = 1 ,8344    ,105,105,105
BEGIN DESCRIPTION:
Mapping XS 552fc8bf
END DESCRIPTION:
XS GIS Cut Line= 4
      1856633.04     13960674.27      1856680.55     13960535.81
      1856643.81      13960259.9      1856651.65      13960083.1
#Sta/Elev= 30
  4743.4 1930.62  4837.8 1925.03  4920.9  1924.3  4951.1 1918.35  4963.8  1916.9
  4991.5 1914.64  5011.7 1911.41  5018.4 1911.39  5018.9 1910.89  5024.6 1910.89
  5025.1 1911.39  5046.2 1913.65  5063.4 1916.88  5092.4 1919.79  5102.5 1921.58
  5119.4 1929.29  5124.5 1928.21  5132.7 1928.62    5163 1939.74  5168.1 1942.54
  5173.1 1942.54    5183 1946.42  5193.1 1949.38  5253.1 1963.47  5283.1 1966.85
    5303 1967.59    5308 1969.06  5313.2 1969.53  5323.2 1970.21  5345.1 1970.32
#Mann= 6 ,-1 , 0
  4743.4    .035       0  4963.8     .07       0  5018.4     .05       0
  5025.1     .07       0  5063.4    .035       0    5163     .07       0
Bank Sta=5018.4,5025.1
XS Rating Curve= 0 ,0
Exp/Cntr=0.3,0.1

Type RM Length L Ch R = 1 ,8239    ,75,75,75
BEGIN DESCRIPTION:
Mapping XS 5e4006c2
END DESCRIPTION:
XS GIS Cut Line= 3
      1856691.86     13960698.88      1856763.99     13960496.35
      1856663.45     13960150.77
#Sta/Elev= 30
    4737 1928.25  4759.2 1928.65  4820.8 1925.24  4881.1 1923.77  4932.2  1922.5
  4944.1 1921.04  4946.7 1919.23  4947.2 1918.73  4953.4 1919.23  4962.4 1921.65
  4967.6 1921.12  4969.9 1922.11  5006.4 1930.81  5047.1 1932.04  5073.4 1930.45
    5086 1931.73  5109.6  1931.3  5161.7 1932.39  5179.2 1940.38  5184.4 1940.27
  5189.4 1942.73  5212.7 1952.99  5217.9 1951.58    5245 1960.89  5251.4  1964.5
  5256.6 1962.29  5265.8  1964.7    5285 1967.19  5290.2 1965.95  5311.9 1968.24
#Mann= 8 ,-1 , 0
    4737    .035       0  4881.1     .07       0  4946.7    .035       0
  4953.4     .07       0  4969.9    .035       0    5086     .07       0
  5109.6    .035       0  5189.4     .07       0
Bank Sta=4946.7,4953.4
XS Rating Curve= 0 ,0
Exp/Cntr=0.3,0.1

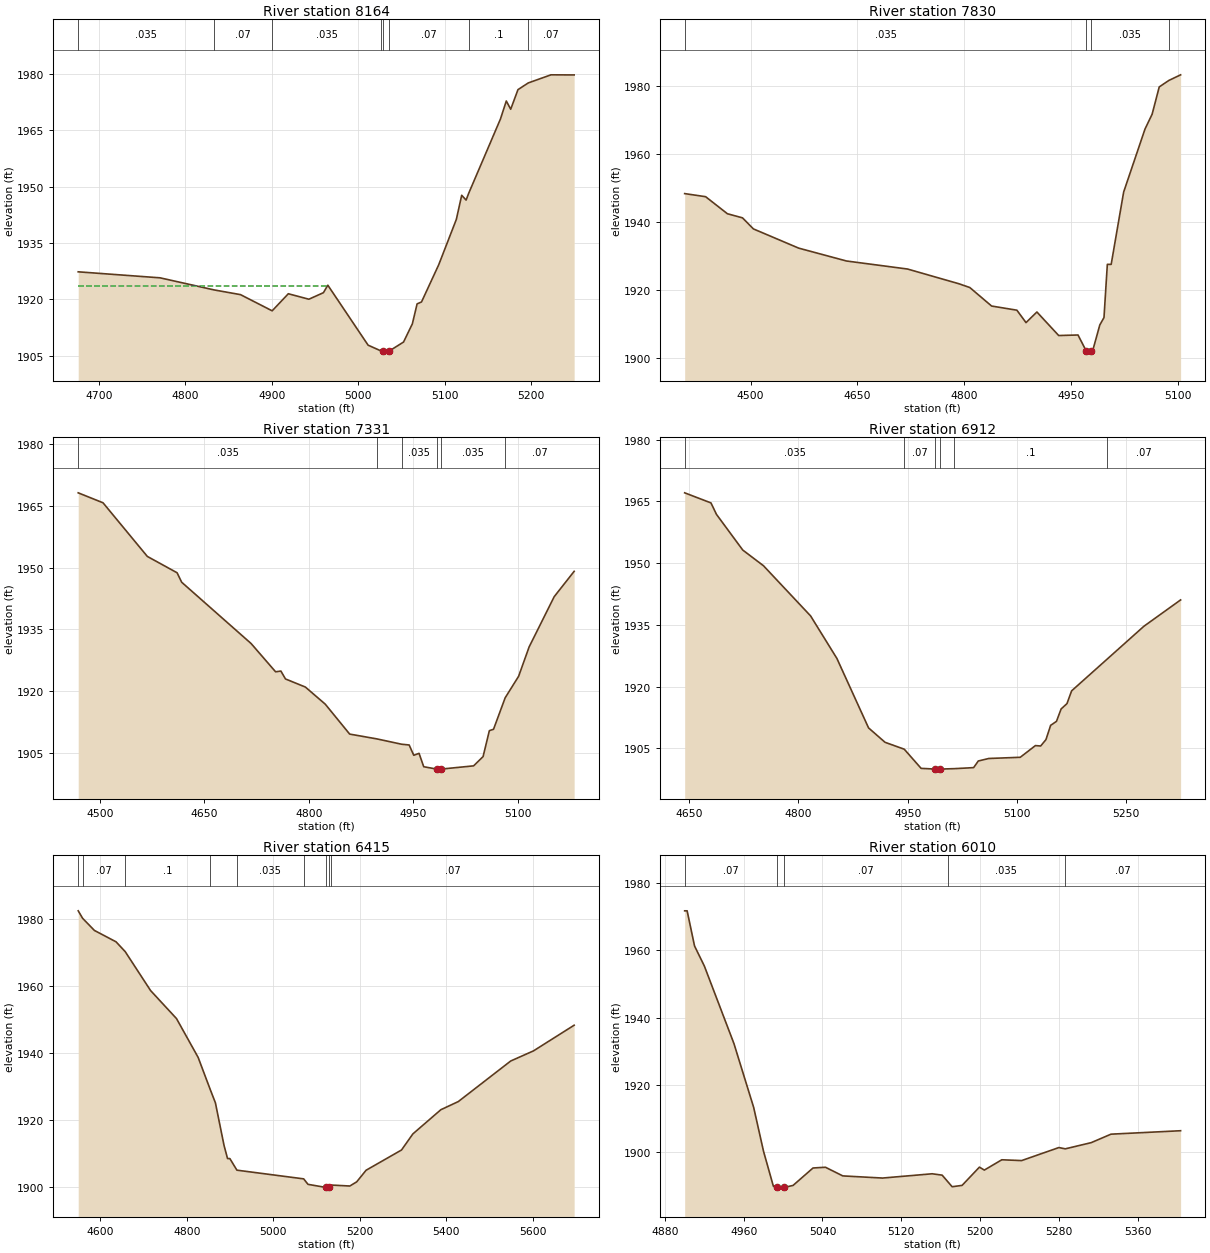
Type RM Length L Ch R = 1 ,8164    ,334,334,334
BEGIN DESCRIPTION:
Mapping XS 65bdc893
END DESCRIPTION:
XS GIS Cut Line= 3
      1856726.51     13960704.26      1856814.49     13960454.99
      1856755.35     13960151.24
#Sta/Elev= 30
  4675.9 1927.33  4770.6 1925.73  4833.3  1922.5  4863.7 1921.25  4900.3 1916.94
    4919 1921.49  4942.8 1920.03  4959.6 1921.77  4964.7 1923.77  5011.3 1907.79
  5026.7 1906.21  5028.6 1906.17  5029.1 1905.67  5035.3 1906.17  5052.3 1908.62
  5062.5 1913.47    5068 1918.79  5073.1  1919.3    5093  1929.2  5113.4  1941.3
  5119.6 1947.72  5124.7 1946.44  5127.5 1948.14  5164.4 1968.02  5171.2 1972.84
  5176.3 1970.64  5184.7 1975.86  5196.6 1977.65  5222.9 1979.81  5249.7 1979.78
#Mann= 8 ,-1 , 0
  4675.9    .035       0  4833.3     .07       0  4900.3    .035       0
  5026.7     .07       0  5028.6    .035       0  5035.3     .07       0
  5127.5      .1       0  5196.6     .07       0
#XS Ineff= 2 , 0
         4965.37 1923.66
Permanent Ineff=
       F       F
Bank Sta=5028.6,5035.3
XS Rating Curve= 0 ,0
Exp/Cntr=0.3,0.1

Type RM Length L Ch R = 1 ,7830    ,499,499,499
BEGIN DESCRIPTION:
Byas Branch 14.0
END DESCRIPTION:
XS GIS Cut Line= 3
      1856520.11     13960892.54        1857025.       13960575.
      1857124.96       13960575.
#Sta/Elev= 30
  4407.5 1948.38  4436.9 1947.47  4467.5 1942.46  4488.7 1941.25    4504    1938
  4567.6 1932.35  4634.7 1928.57  4720.4 1926.21  4792.6 1921.88  4807.9 1920.77
  4838.5 1915.33    4874 1914.11  4886.8 1910.46  4902.1 1913.58  4932.7 1906.66
  4959.8 1906.82  4971.7 1901.99  4972.2 1901.49  4978.4 1901.99    4981 1902.63
  4990.4 1909.75  4996.3 1911.95    5001 1927.58  5006.4 1927.58  5023.9 1948.83
  5053.9 1967.36  5063.9 1971.72  5073.9 1979.74  5087.5 1981.65  5103.9 1983.29
#Mann= 4 ,-1 , 0
  4407.5    .035       0  4971.7     .05       0  4978.4    .035       0
  5087.5      .1       0
Bank Sta=4971.7,4978.4
XS Rating Curve= 0 ,0
Exp/Cntr=0.3,0.1

Type RM Length L Ch R = 1 ,7331    ,419,419,419
BEGIN DESCRIPTION:
Byas Branch 13.0
END DESCRIPTION:
XS GIS Cut Line= 3
      1856675.02     13961474.98        1857025.       13961075.
      1857175.04     13960974.97
#Sta/Elev= 30
  4469.1 1968.18  4504.7 1965.76  4568.3 1952.73    4611 1948.76  4617.6 1946.46
  4717.3 1931.56  4752.4  1924.7    4760 1924.88  4766.6 1922.96  4795.1    1921
  4823.6 1916.85  4858.7 1909.57  4897.8  1908.4  4933.1 1907.11  4944.1 1906.92
  4950.7 1904.42  4958.3 1904.89    4965 1901.64  4983.4 1901.07  4983.9 1900.57
  4990.2 1901.07  5036.6 1901.85  5050.2  1904.1  5059.2  1910.4  5065.2 1910.74
  5081.9 1918.39  5101.2 1923.61  5116.3 1930.75  5152.3 1942.96  5180.9 1949.11
#Mann= 6 ,-1 , 0
  4469.1    .035       0  4897.8     .07       0  4933.1    .035       0
  4983.4    .035       0  4990.2    .035       0  5081.9     .07       0
Bank Sta=4983.4,4990.2
XS Rating Curve= 0 ,0
Exp/Cntr=0.3,0.1

Type RM Length L Ch R = 1 ,6912    ,497,497,497
BEGIN DESCRIPTION:
Byas Branch 12.0
END DESCRIPTION:
XS GIS Cut Line= 3
      1856774.97     13961625.02        1857075.       13961425.
      1857274.97     13961175.03
#Sta/Elev= 30
  4643.9 1967.06    4680 1964.61  4687.5 1961.84  4723.6 1953.17  4752.1 1949.35
  4816.7 1937.18  4852.8 1926.86  4896.3 1909.98  4918.9 1906.49  4945.3 1904.81
  4968.4 1900.16  4987.5 1899.99    4988 1899.49  4994.4 1899.99  5014.2 1900.09
  5040.5 1900.34  5046.9 1901.95  5061.3 1902.56  5104.5 1902.85  5125.3 1905.69
  5132.5 1905.59  5139.8 1907.15  5146.2 1910.61  5154.2 1911.57  5160.6 1914.59
  5168.6 1915.88    5175 1918.98  5222.9 1926.55  5274.2 1934.66  5324.6 1941.06
#Mann= 6 ,-1 , 0
  4643.9    .035       0  4945.3     .07       0  4987.5     .05       0
  4994.4     .07       0  5014.2      .1       0  5222.9     .07       0
Bank Sta=4987.5,4994.4
XS Rating Curve= 0 ,0
Exp/Cntr=0.3,0.1

Type RM Length L Ch R = 1 ,6415    ,405,405,405
BEGIN DESCRIPTION:
Mapping XS 84a8d892
END DESCRIPTION:
XS GIS Cut Line= 4
      1857227.52     13962262.49      1857222.36     13961913.87
      1857414.85     13961573.24      1857474.09     13961169.78
#Sta/Elev= 30
  4548.5 1982.52  4558.8 1980.27    4586 1976.65    4636 1973.25  4657.2 1970.32
    4716 1958.66    4776 1950.27    4826 1938.67    4854 1929.06    4866 1925.07
    4886  1912.3  4894.1 1908.39  4899.4 1908.39  4915.8 1904.91  5070.3 1902.31
  5080.3 1900.67  5121.9 1899.74  5122.4 1899.24  5129.2 1899.74  5132.5 1900.47
  5177.1 1900.17    5193 1901.42  5214.7 1904.89  5296.7 1910.95    5323 1915.77
  5387.7    1923  5428.1 1925.44  5549.4 1937.58  5602.1 1940.61  5696.2 1948.29
#Mann= 9 ,-1 , 0
  4548.5      .1       0  4558.8     .07       0  4657.2      .1       0
    4854     .07       0  4915.8    .035       0  5070.3      .1       0
  5121.9    .035       0  5129.2      .1       0  5132.5     .07       0
Bank Sta=5121.9,5129.2
XS Rating Curve= 0 ,0
Exp/Cntr=0.3,0.1

Type RM Length L Ch R = 1 ,6010    ,949,949,949
BEGIN DESCRIPTION:
Byas Branch 11.0
END DESCRIPTION:
XS GIS Cut Line= 3
        1857575.     13962124.95        1857575.       13962025.
        1857525.     13961624.97
#Sta/Elev= 30
  4900.2 1971.71  4902.7 1971.71  4910.2 1961.27  4920.2 1955.28  4950.2 1932.25
  4970.2 1913.29  4980.2 1900.25  4990.2 1889.86    4994 1889.52  4994.5 1889.02
  5001.3 1889.52  5010.2 1890.13  5030.4  1895.3    5043 1895.52  5060.6 1892.95
  5100.9 1892.31  5151.3 1893.58  5161.4 1893.17  5166.9  1891.3  5171.5 1889.73
  5181.6 1890.13  5199.2 1895.55  5204.2 1894.68  5221.9 1897.74    5242  1897.5
  5279.8 1901.37  5286.3 1900.99  5312.6 1902.83  5332.7 1905.35  5403.3 1906.37
#Mann= 5 ,-1 , 0
  4900.2     .07       0    4994     .05       0  5001.3     .07       0
  5166.9    .035       0  5286.3     .07       0
Bank Sta=4994,5001.3
XS Rating Curve= 0 ,0
Exp/Cntr=0.3,0.1