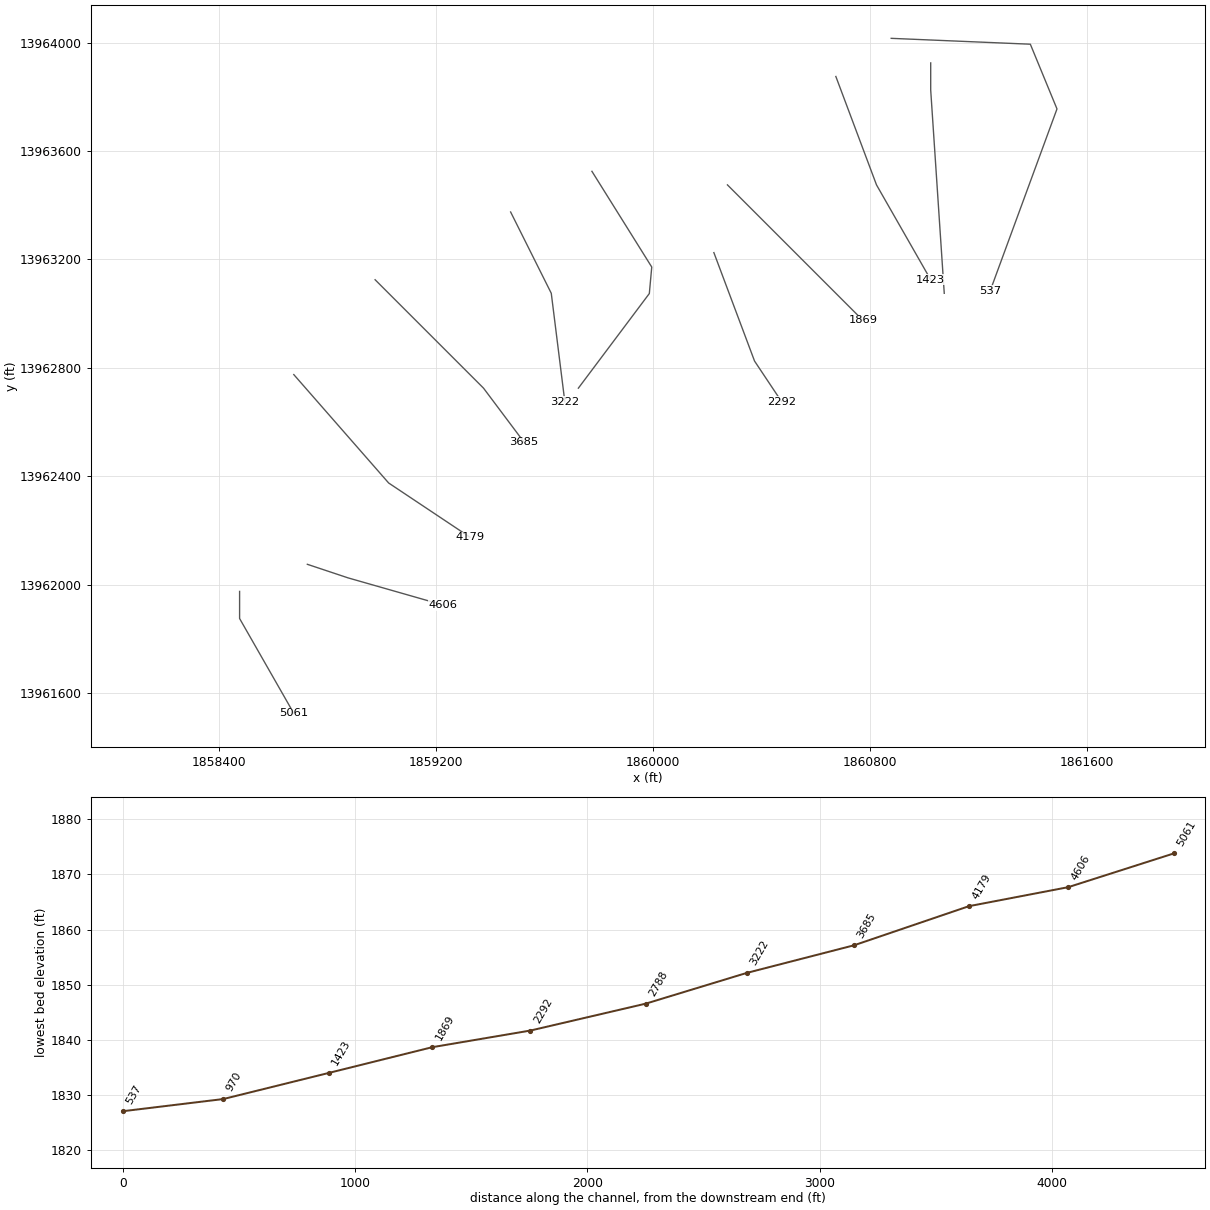
HEC-RAS study Byas Branch.prj: Byas Branch Base Level Engineering

--- Byas Branch.g01 (geometry) --- (continued)

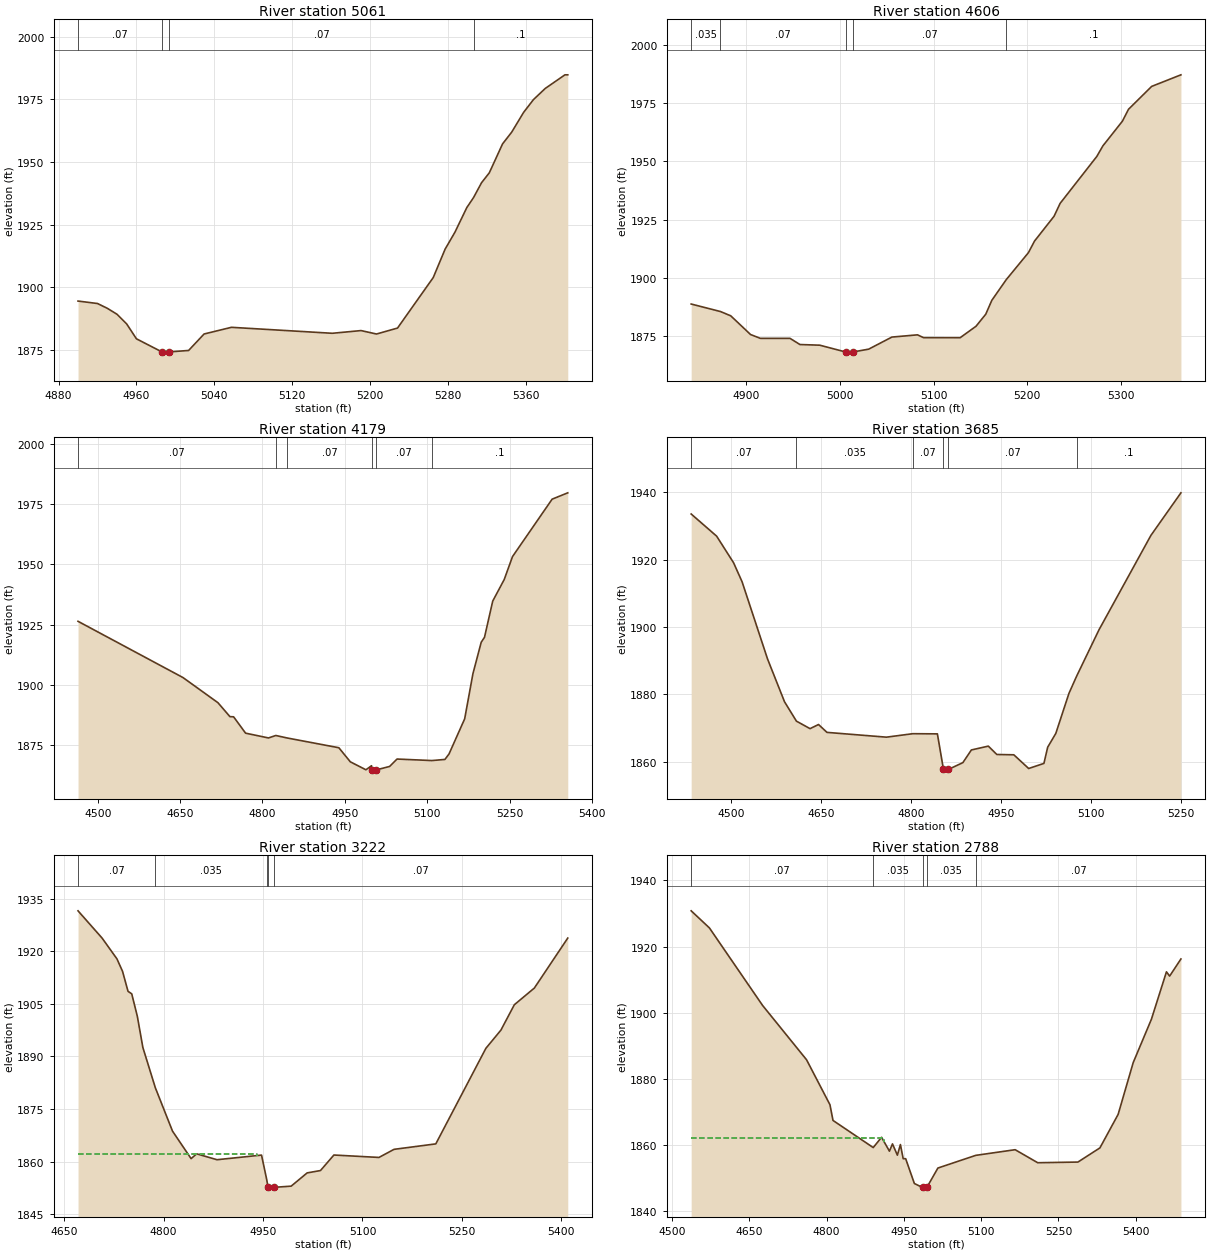
Type RM Length L Ch R = 1 ,5061    ,455,455,455
BEGIN DESCRIPTION:
Byas Branch 10.0
END DESCRIPTION:
XS GIS Cut Line= 3
        1858475.     13961974.96        1858475.       13961875.
      1858675.01     13961524.98
#Sta/Elev= 30
    4900 1894.55    4920 1893.57    4930 1891.68    4940  1889.3    4950 1885.42
    4960  1879.5  4986.1 1874.29  4986.6 1873.79  4993.9 1874.29  5013.6 1874.85
  5029.5 1881.42  5057.6 1884.08  5161.2  1881.7  5190.7 1882.78  5206.6 1881.41
  5228.2 1883.78  5264.9 1903.92  5277.1 1915.25  5287.2 1922.02  5299.4 1931.83
  5306.3 1935.81  5314.5 1941.72  5322.5 1945.69  5336.1 1957.21  5345.5  1961.9
  5357.7 1969.76  5367.8 1974.85    5380 1979.33  5400.2 1984.75  5403.1 1984.75
#Mann= 4 ,-1 , 0
    4900     .07       0  4986.1     .05       0  4993.9     .07       0
  5306.3      .1       0
Bank Sta=4986.1,4993.9
XS Rating Curve= 0 ,0
Exp/Cntr=0.3,0.1

Type RM Length L Ch R = 1 ,4606    ,427,427,427
BEGIN DESCRIPTION:
Byas Branch 9.0
END DESCRIPTION:
XS GIS Cut Line= 3
      1858724.97     13962075.01        1858875.       13962025.
      1859225.05     13961924.99
#Sta/Elev= 30
  4841.6 1888.75  4872.8 1885.53  4883.8 1883.69  4904.9 1875.66  4915.4 1874.01
    4947 1874.01  4957.6 1871.36  4978.7 1871.08  5006.2 1868.17  5006.7 1867.67
  5014.1 1868.17  5030.9 1869.38  5055.6 1874.56  5082.9 1875.52  5089.4 1874.31
  5128.4 1874.29  5145.3  1879.2  5155.7 1884.38  5162.2 1890.36  5177.5 1899.19
  5201.2 1910.81  5207.7 1915.78  5228.5 1926.42    5235 1931.97  5274.1 1952.11
  5280.6 1956.66  5301.4 1967.25  5307.9 1972.36  5332.6 1982.19  5363.8 1987.16
#Mann= 5 ,-1 , 0
  4841.6    .035       0  4872.8     .07       0  5006.2     .05       0
  5014.1     .07       0  5177.5      .1       0
Bank Sta=5006.2,5014.1
XS Rating Curve= 0 ,0
Exp/Cntr=0.3,0.1

Type RM Length L Ch R = 1 ,4179    ,494,494,494
BEGIN DESCRIPTION:
Byas Branch 8.0
END DESCRIPTION:
XS GIS Cut Line= 3
      1858674.97     13962775.03        1859025.       13962375.
        1859325.       13962175.
#Sta/Elev= 30
    4464 1926.36  4655.3 1903.02  4718.9  1892.6  4740.7 1886.83  4747.4 1886.76
  4769.2 1879.98  4810.9 1877.99  4824.3 1879.01  4844.4    1878  4939.1 1873.93
    4960 1868.09  4988.4 1864.79  4998.6 1866.46  4999.1 1864.73  4999.6 1864.23
    5007 1864.73  5031.6 1866.17  5045.1 1869.24  5108.9 1868.61  5132.3 1869.08
  5139.8 1871.35  5168.3 1885.92  5183.3  1904.6  5198.4 1917.67  5204.4 1919.73
  5219.4 1934.75  5240.4 1943.73  5255.4  1953.2  5327.6 1977.02  5356.1 1979.65
#Mann= 6 ,-1 , 0
    4464     .07       0  4824.3    .035       0  4844.4     .07       0
  4999.1     .05       0    5007     .07       0  5108.9      .1       0
Bank Sta=4999.1,5007
XS Rating Curve= 0 ,0
Exp/Cntr=0.3,0.1

Type RM Length L Ch R = 1 ,3685    ,463,463,463
BEGIN DESCRIPTION:
Byas Branch 7.0
END DESCRIPTION:
XS GIS Cut Line= 3
      1858975.02     13963124.98        1859375.       13962725.
      1859525.03     13962524.96
#Sta/Elev= 30
  4434.1 1933.54  4476.5 1926.96  4504.8 1919.03  4518.9  1913.4  4561.3 1890.47
  4589.6 1877.75  4609.4    1872  4632.1 1869.77  4646.2    1871  4660.3 1868.66
  4759.3 1867.24  4803.3 1868.27  4844.2 1868.22  4854.3 1857.65  4854.8 1857.15
  4862.4 1857.65  4886.6 1859.67  4900.8 1863.44    4929 1864.58  4943.2 1862.09
  4971.5    1862  4996.2 1857.93  5021.6 1859.44  5027.9 1864.26  5041.4 1868.35
  5063.3 1880.25  5076.1 1885.36  5113.3 1899.12  5199.8 1927.18  5249.8 1939.83
#Mann= 6 ,-1 , 0
  4434.1     .07       0  4609.4    .035       0  4803.3     .07       0
  4854.3     .05       0  4862.4     .07       0  5076.1      .1       0
Bank Sta=4854.3,4862.4
XS Rating Curve= 0 ,0
Exp/Cntr=0.3,0.1

Type RM Length L Ch R = 1 ,3222    ,434,434,434
BEGIN DESCRIPTION:
Byas Branch 6.0
END DESCRIPTION:
XS GIS Cut Line= 3
      1859475.01     13963374.98        1859625.       13963075.
        1859675.       13962675.
#Sta/Elev= 30
  4671.1 1931.53  4707.4 1923.75  4729.8 1917.82  4738.2 1914.28  4746.5 1908.56
  4752.1 1907.85  4760.5 1901.46  4768.9 1892.52  4787.7 1881.04  4813.6 1868.67
  4841.6 1860.83    4850  1862.2  4880.7 1860.52  4947.8 1861.84  4955.5 1854.97
  4957.7 1852.63  4958.2 1852.13  4965.9 1852.63  4992.5 1852.98  5016.6 1856.76
  5036.7 1857.43  5056.9 1861.86  5124.9 1861.17  5147.6 1863.48  5210.6 1865.04
  5286.1  1892.3  5308.8  1897.5    5329 1904.73  5359.2  1909.5  5409.6 1923.76
#Mann= 5 ,-1 , 0
  4671.1     .07       0  4787.7    .035       0  4955.5     .07       0
  4957.7     .05       0  4965.9     .07       0
#XS Ineff= 2 , 0
          4940.7 1862.22
Permanent Ineff=
       F       F
Bank Sta=4957.7,4965.9
XS Rating Curve= 0 ,0
Exp/Cntr=0.3,0.1

Type RM Length L Ch R = 1 ,2788    ,496,496,496
BEGIN DESCRIPTION:
Byas Branch 5.0
END DESCRIPTION:
XS GIS Cut Line= 4
      1859774.99     13963525.02      1859995.75     13963171.81
      1859986.82     13963074.09      1859725.01     13962725.01
#Sta/Elev= 30
  4536.9  1930.8  4572.3 1925.63  4675.5 1902.18    4761 1885.71  4806.4 1872.11
  4812.3 1867.36  4890.4 1859.15  4906.6 1862.26  4921.9 1858.06  4927.8 1860.26
  4937.3 1856.85  4943.2 1860.06  4948.6 1855.78  4953.4 1855.78  4970.3 1848.27
  4986.2 1847.07  4986.7 1846.57  4994.5 1847.07    5016 1852.95  5089.5 1856.79
    5166  1858.5  5209.8 1854.56  5287.9 1854.76  5330.6 1859.05    5366  1869.2
  5395.2 1884.85  5430.6 1897.99  5459.8 1912.34    5466 1911.05  5487.9 1916.23
#Mann= 5 ,-1 , 0
  4536.9     .07       0  4890.4    .035       0  4986.2    .035       0
  4994.5    .035       0  5089.5     .07       0
#XS Ineff= 2 , 0
         4911.63  1861.9
Permanent Ineff=
       F       F
Bank Sta=4986.2,4994.5
XS Rating Curve= 0 ,0
Exp/Cntr=0.3,0.1

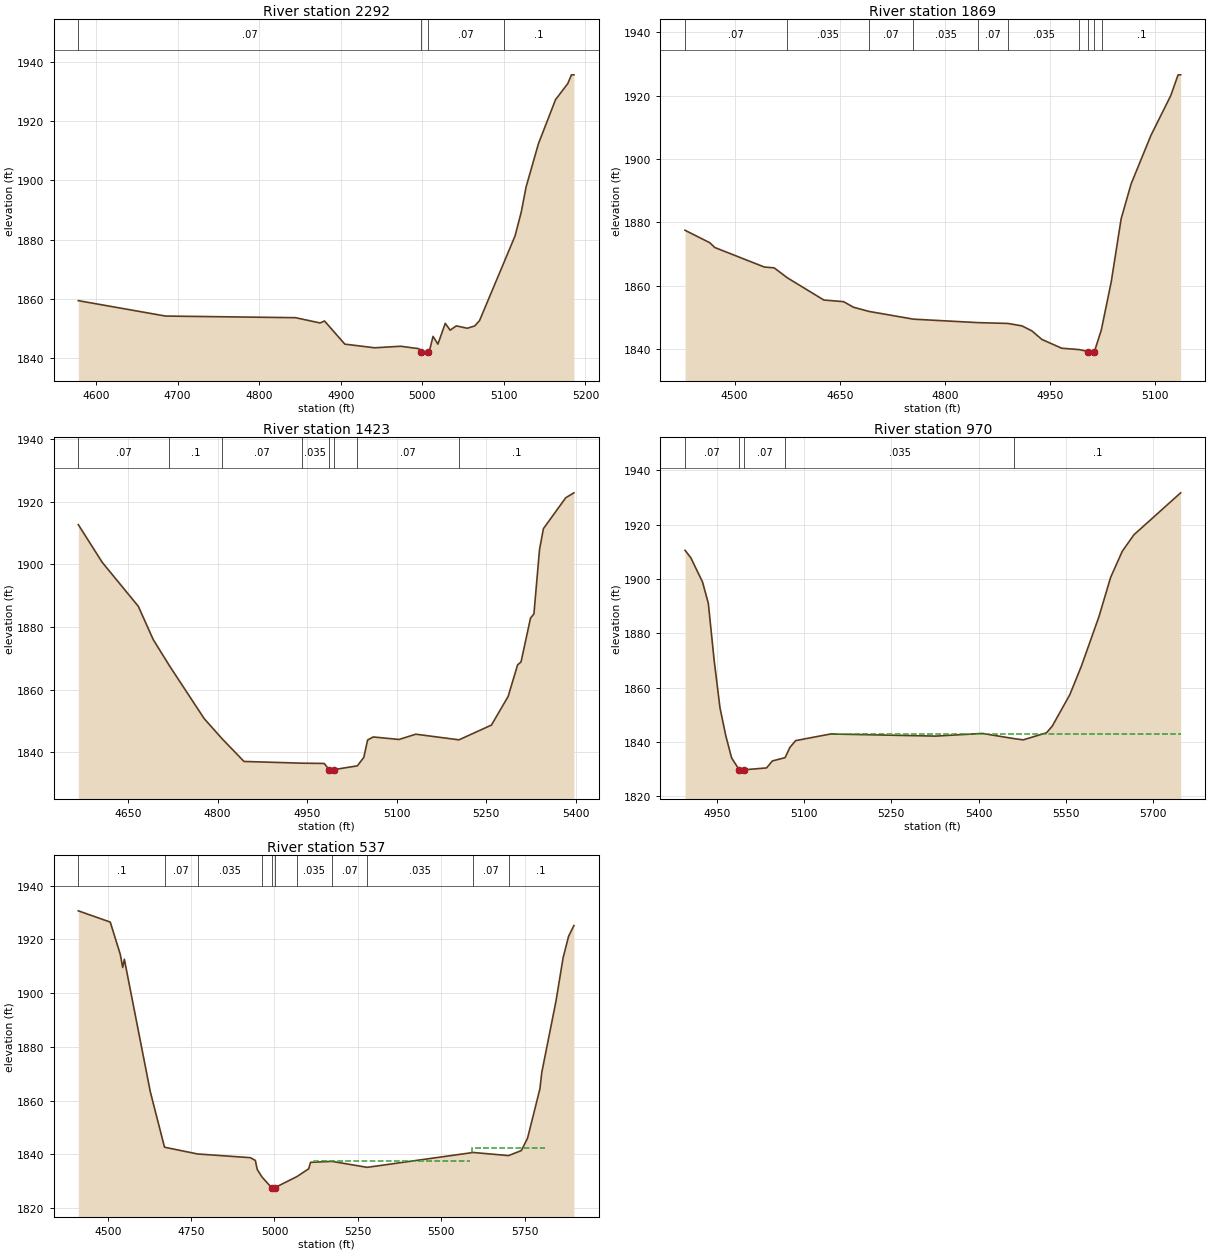
Type RM Length L Ch R = 1 ,2292    ,423,423,423
BEGIN DESCRIPTION:
Byas Branch 4.0
END DESCRIPTION:
XS GIS Cut Line= 3
      1860224.98     13963225.04        1860375.       13962825.
      1860474.99     13962675.02
#Sta/Elev= 30
  4578.3 1859.39  4685.1  1854.2  4844.5 1853.65  4874.7 1851.87  4880.1 1852.54
    4905 1844.73  4941.5  1843.5  4973.5 1844.02  4995.8 1843.19  4998.5  1842.2
    4999  1841.7  5007.2  1842.2  5008.5  1842.2  5013.1 1847.34  5019.1 1844.74
  5028.1 1851.74  5034.1 1849.44  5041.6 1850.89  5055.1 1850.09  5064.1 1850.85
  5070.1 1852.65  5099.7 1872.05  5113.7 1881.25  5121.2  1889.2  5127.2 1897.74
  5142.3 1912.28  5163.3 1927.17  5178.3 1932.58  5182.8 1935.53  5185.8 1935.53
#Mann= 4 ,-1 , 0
  4578.3     .07       0  4998.5     .05       0  5007.2     .07       0
  5099.7      .1       0
Bank Sta=4998.5,5007.2
XS Rating Curve= 0 ,0
Exp/Cntr=0.3,0.1

Type RM Length L Ch R = 1 ,1869    ,446,446,446
BEGIN DESCRIPTION:
Byas Branch 3.0
END DESCRIPTION:
XS GIS Cut Line= 3
      1860275.03     13963474.97        1860675.       13963075.
      1860775.02     13962974.98
#Sta/Elev= 30
  4429.3 1877.49  4464.6 1873.56  4471.7 1872.05  4542.4 1865.88  4556.5 1865.62
  4575.2 1862.48  4627.3 1855.46  4655.5 1854.94  4669.7 1853.17  4691.7 1851.86
  4755.2 1849.41  4847.8 1848.31  4889.9 1848.06  4910.1 1847.28  4924.2 1845.71
  4938.4 1843.01  4966.7 1840.23  4991.9 1839.79  5004.7 1839.18  5005.2 1838.68
  5013.4 1839.18  5023.2 1845.97  5024.7 1847.58  5037.4 1861.22  5051.5 1881.09
  5065.7 1892.11  5093.9 1907.41  5122.2 1919.99  5132.8  1926.6  5136.4  1926.6
#Mann= 10 ,-1 , 0
  4429.3     .07       0  4575.2    .035       0  4691.7     .07       0
  4755.2    .035       0  4847.8     .07       0  4889.9    .035       0
  4991.9     .07       0  5004.7     .05       0  5013.4     .07       0
  5024.7      .1       0
Bank Sta=5004.7,5013.4
XS Rating Curve= 0 ,0
Exp/Cntr=0.3,0.1

Type RM Length L Ch R = 1 ,1423    ,453,453,453
BEGIN DESCRIPTION:
Byas Branch 2.0
END DESCRIPTION:
XS GIS Cut Line= 3
      1860675.01     13963874.96        1860825.       13963475.
      1861025.01     13963124.98
#Sta/Elev= 30
  4566.8  1912.7  4606.8 1900.68  4667.3 1886.64  4692.2 1876.05  4719.5 1867.65
  4777.7 1850.77  4807.6 1844.36  4844.4  1837.1    4941 1836.55  4978.8 1836.46
  4986.9 1834.51  4987.4 1834.01  4995.7 1834.51  5034.3  1835.7  5045.1  1838.4
  5051.5 1843.95  5060.9 1844.92  5104.1 1844.12  5132.2  1845.8  5204.5    1844
  5258.9 1848.71  5286.9 1857.85  5302.8 1867.96  5308.5 1868.86  5324.4 1882.86
  5330.1 1884.19  5339.5 1904.74    5346 1911.41  5383.4 1921.29  5397.1 1922.86
#Mann= 8 ,-1 , 0
  4566.8     .07       0  4719.5      .1       0  4807.6     .07       0
    4941    .035       0  4986.9    .035       0  4995.7    .035       0
  5034.3     .07       0  5204.5      .1       0
#XS Ineff= 2 , 0
                         5134.48         1845.66
Permanent Ineff=
       F       F
Bank Sta=4986.9,4995.7
XS Rating Curve= 0 ,0
Exp/Cntr=0.3,0.1

Type RM Length L Ch R = 1 ,970     ,433,433,433
BEGIN DESCRIPTION:
Byas Branch 1.0
END DESCRIPTION:
XS GIS Cut Line= 3
        1861025.     13963925.01        1861025.       13963825.
        1861075.     13963074.97
#Sta/Elev= 30
  4895.6 1910.56  4905.6 1907.79  4925.6 1898.91  4935.6 1891.06  4945.6 1870.12
  4955.6 1852.64  4965.6 1842.36  4975.6 1834.15  4988.7 1829.79  4989.2 1829.29
  4997.5 1829.79  5035.7 1830.47  5045.7 1833.04  5067.5 1834.25  5075.8 1838.03
  5085.8 1840.53  5145.9 1842.96  5326.3 1842.18  5406.5 1843.16  5460.8 1841.26
  5476.7  1840.8  5516.8 1843.39  5526.8  1845.9  5556.9 1857.44  5576.9 1868.03
    5607  1886.2    5627 1900.61  5647.1 1910.25  5667.1 1916.29  5747.3 1931.71
#Mann= 5 ,-1 , 0
  4895.6     .07       0  4988.7     .05       0  4997.5     .07       0
  5067.5    .035       0  5460.8      .1       0
#XS Ineff= 2 , 0
                         5144.59         1842.99
Permanent Ineff=
       F       F
Bank Sta=4988.7,4997.5
XS Rating Curve= 0 ,0
Exp/Cntr=0.3,0.1

Type RM Length L Ch R = 1 ,537     ,0,0,0
BEGIN DESCRIPTION:
Byas Branch 0.0
END DESCRIPTION:
XS GIS Cut Line= 4
      1860879.26     13964015.71      1861392.64     13963994.04
      1861490.96     13963755.24      1861244.67     13963084.63
#Sta/Elev= 30
  4411.6 1930.66  4507.4 1926.47  4537.4 1914.49  4544.7 1909.56  4549.7 1912.63
  4627.5 1863.33  4670.2 1842.68  4769.1 1840.17  4927.6 1838.79  4942.7 1837.76
  4948.1 1834.44  4962.3 1831.64  4991.6 1827.58  4992.1 1827.08  5000.4 1827.58
  5067.2 1831.74  5102.6 1834.65  5108.2 1837.05  5172.2 1837.41  5278.1 1835.19
  5596.1 1840.72  5702.1 1839.56  5740.4 1841.43  5759.2  1846.1  5796.1 1864.39
  5801.8 1870.55  5844.4 1897.08  5865.7 1913.19  5882.2 1921.21  5898.1 1925.17
#Mann= 11 ,-1 , 0
  4411.6      .1       0  4670.2     .07       0  4769.1    .035       0
  4962.3      .1       0  4991.6     .05       0  5000.4      .1       0
  5067.2    .035       0  5172.2     .07       0  5278.1    .035       0
  5596.1     .07       0  5702.1      .1       0
#XS Ineff= 2 ,-1
 5118.97 5587.621837.471 5591.23 5812.13 1842.35
Permanent Ineff=
       F       F
Bank Sta=4991.6,5000.4
XS Rating Curve= 0 ,0
Exp/Cntr=0.3,0.1

Chan Stop Cuts=-1
Use User Specified Reach Order=0
Composite Channel Slope=5