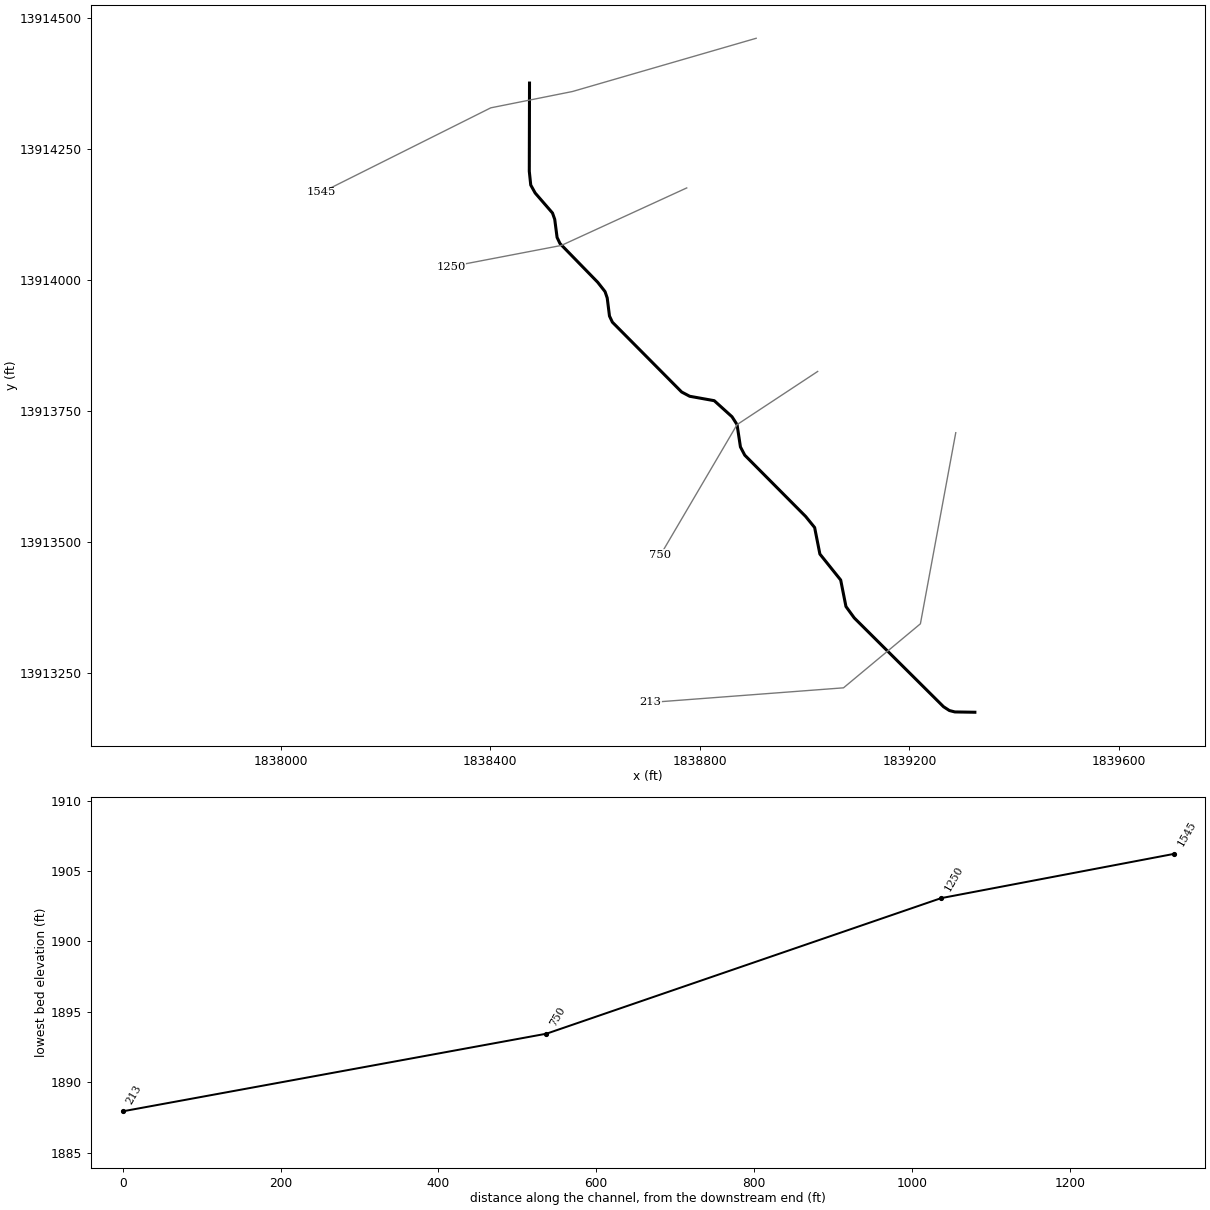
--- Cherry Creek_2.prj (project) ---

Proj Title=Cherry Creek_2 Base Level Engineering
Current Plan=p01
Default Exp/Contr=0.3,0.1
English Units
Geom File=g01
Flow File=f01
Plan File=p01
Y Axis Title=Elevation
X Axis Title(PF)=Main Channel Distance
X Axis Title(XS)=Station
BEGIN DESCRIPTION:
Cherry Creek_2
END DESCRIPTION:
DSS Export Rating Curves= 0
DSS Export Rating Curve Sorted= 0
DSS Export Volume Flow Curves= 0
DXF OffsetX= 0
DXF OffsetY= 0
DXF ScaleX= 1
DXF ScaleY= 10

--- Cherry Creek_2.p01 (plan) ---

Plan Title=Multiple Run
Short Identifier=Multiple
Geom File=g01
Flow File=f01
Subcritical Flow
K Sum by GR= 0
Std Step Tol= 0.01
Critical Tol= 0.01
Num of Std Step Trials= 20
Max Error Tol= 0.3
Flow Tol Ratio= 0.001
Split Flow NTrial= 30
Split Flow Tol= 0.02
Split Flow Ratio= 0.02
Log Output Level= 0
Friction Slope Method= 1
Unsteady Friction Slope Method= 2
Unsteady Bridges Friction Slope Method= 1
Parabolic Critical Depth
Global Vel Dist=  1 , 1 , 1
Global Log Level= 0
CheckData=True
Encroach Param= -1, 0, 0, 0
BEGIN DESCRIPTION:
Multiple Run
END DESCRIPTION:

--- Cherry Creek_2.f01 (steady flow) ---

Flow Title=Multiple
Number of Profiles=7
Profile Names=10-year,25-year,50-year,1pct_min,100-year,1pct_plu,500-year
River Rch & RM= Cherry Creek_2,Reach-1,1545
    1566    2761    3935    2710    5407   10787   10091
Boundary for River Rch & Prof#=Cherry Creek_2,Reach-1,1
Up Type=0
Dn Type=3
Dn Slope=0.005
Boundary for River Rch & Prof#=Cherry Creek_2,Reach-1,2
Up Type=0
Dn Type=3
Dn Slope=0.005
Boundary for River Rch & Prof#=Cherry Creek_2,Reach-1,3
Up Type=0
Dn Type=3
Dn Slope=0.005
Boundary for River Rch & Prof#=Cherry Creek_2,Reach-1,4
Up Type=0
Dn Type=3
Dn Slope=0.005
Boundary for River Rch & Prof#=Cherry Creek_2,Reach-1,5
Up Type=0
Dn Type=3
Dn Slope=0.005
Boundary for River Rch & Prof#=Cherry Creek_2,Reach-1,6
Up Type=0
Dn Type=3
Dn Slope=0.005
Boundary for River Rch & Prof#=Cherry Creek_2,Reach-1,7
Up Type=0
Dn Type=3
Dn Slope=0.005

--- Cherry Creek_2.g01 (geometry) ---

Geom Title=Existing Conditions

River Reach=Cherry Creek_2,Reach-1
Reach XY= 30
      1838475.00     13914375.00      1838474.59     13914206.65
      1838477.35     13914180.52      1838485.79     13914165.33
      1838518.86     13914127.17      1838523.12     13914115.13
      1838527.61     13914080.63      1838533.16     13914068.95
      1838605.17     13913995.07      1838619.13     13913977.28
      1838623.29     13913965.20      1838627.64     13913930.64
      1838633.16     13913918.95      1838765.34     13913785.79
      1838780.68     13913777.66      1838827.54     13913769.25
      1838861.51     13913738.56      1838871.11     13913723.57
      1838877.55     13913681.09      1838885.79     13913665.34
      1839001.99     13913548.47      1839019.17     13913527.30
      1839029.19     13913476.74      1839068.90     13913427.19
      1839078.95     13913376.63      1839094.78     13913354.91
      1839265.21     13913185.51      1839276.36     13913178.27
      1839286.84     13913175.59      1839325.00     13913175.00

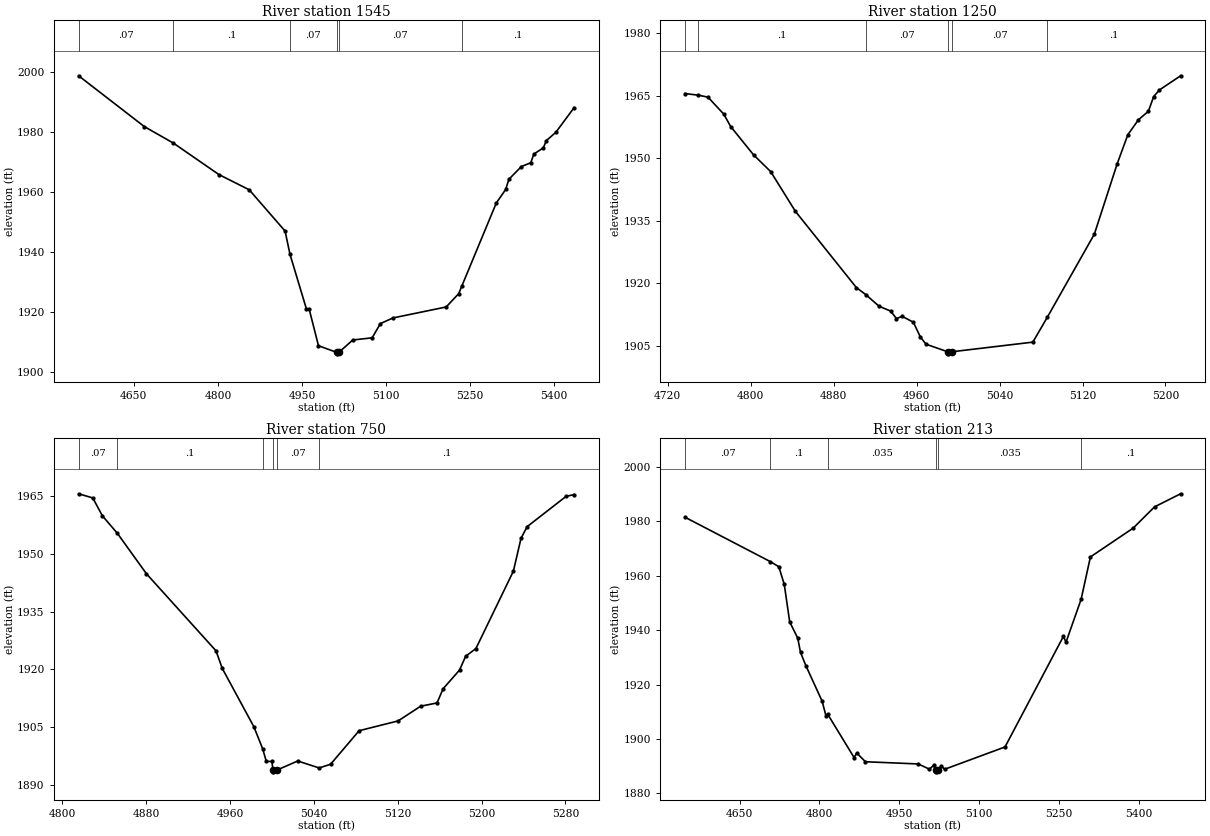
Type RM Length L Ch R = 1,1545,295,295,295
BEGIN DESCRIPTION:
Cherry Creek 2 3.0
END DESCRIPTION:
XS GIS Cut Line= 4
      1838907.56     13914460.42      1838556.95     13914358.90
      1838401.06     13914327.76      1838078.39     13914166.50
#Sta/Elev= 30
  4551.4 1998.87  4668.6 1981.95  4720.6 1976.43  4801.7 1965.97  4856.0 1960.87
  4920.0 1947.12  4928.7 1939.40  4958.0 1921.21  4963.1 1921.02  4979.6 1908.91
  5012.1 1906.71  5012.3 1906.21  5016.1 1906.71  5040.8 1910.82  5075.4 1911.55
  5090.2 1916.29  5112.6 1918.17  5207.6 1921.83  5230.0 1926.28  5235.2 1928.65
  5297.1 1956.49  5313.9 1961.01  5319.5 1964.38  5341.8 1968.61  5358.6 1969.89
  5364.2 1972.79  5381.0 1974.85  5386.6 1977.30  5403.3 1980.01  5436.1 1988.28
#Mann=6,-1,0
  4551.4    0.07       0  4720.6     0.1       0  4928.7    0.07       0
  5012.1    0.05       0  5016.1    0.07       0  5235.2     0.1       0
Bank Sta=5012.1,5016.1
Exp/Cntr=0.3,0.1

Type RM Length L Ch R = 1,1250,500,500,500
BEGIN DESCRIPTION:
Cherry Creek 2 2.0
END DESCRIPTION:
XS GIS Cut Line= 3
      1838775.04     13914175.02      1838535.78     13914065.32
      1838325.01     13914025.00
#Sta/Elev= 30
  4736.8 1965.55  4749.3 1965.17  4758.8 1964.70  4774.1 1960.61  4780.8 1957.62
  4802.8 1950.84  4819.3 1946.82  4843.1 1937.30  4901.9 1918.99  4911.1 1917.27
  4923.9 1914.48  4934.9 1913.35  4940.6 1911.54  4946.1 1912.07  4956.9 1910.66
  4963.6 1907.14  4969.1 1905.38  4990.0 1903.57  4990.3 1903.07  4994.1 1903.57
  5072.1 1905.88  5086.0 1911.83  5131.4 1931.80  5153.5 1948.75  5163.7 1955.67
  5173.9 1959.26  5183.5 1961.29  5188.6 1964.83  5194.2 1966.43  5214.6 1969.82
#Mann=6,-1,0
  4736.8    0.07       0  4749.3     0.1       0  4911.1    0.07       0
  4990.0    0.05       0  4994.1    0.07       0  5086.0     0.1       0
Bank Sta=4990,4994.1
Exp/Cntr=0.3,0.1

Type RM Length L Ch R = 1,750,537,537,537
BEGIN DESCRIPTION:
Cherry Creek 2 1.0
END DESCRIPTION:
XS GIS Cut Line= 3
      1839024.99     13913824.99      1838871.11     13913723.57
      1838725.02     13913475.03
#Sta/Elev= 30
  4815.7 1965.52  4829.2 1964.44  4838.3 1959.83  4852.7 1955.25  4880.4 1944.78
  4946.7 1924.82  4952.7 1920.25  4982.8 1905.15  4991.2 1899.44  4994.7 1896.14
  5000.0 1896.14  5001.1 1893.95  5001.4 1893.45  5005.2 1893.95  5024.6 1896.26
  5045.1 1894.46  5056.0 1895.42  5083.2 1904.11  5120.4 1906.65  5141.8 1910.45
  5157.5 1911.31  5163.3 1914.98  5179.0 1919.84  5184.8 1923.40  5194.6 1925.41
  5230.3 1945.45  5237.6 1953.96  5243.4 1956.99  5280.5 1964.83  5288.3 1965.33
#Mann=6,-1,0
  4815.7    0.07       0  4852.7     0.1       0  4991.2    0.07       0
  5001.1    0.05       0  5005.2    0.07       0  5045.1     0.1       0
Bank Sta=5001.1,5005.2
Exp/Cntr=0.3,0.1

Type RM Length L Ch R = 1,213,0,0,0
BEGIN DESCRIPTION:
Cherry Creek 2 0.0
END DESCRIPTION:
XS GIS Cut Line= 4
      1839288.51     13913708.18      1839221.04     13913343.70
      1839074.29     13913221.58      1838706.03     13913193.68
#Sta/Elev= 30
  4547.8 1981.53  4708.0 1965.22  4723.9 1963.34  4734.1 1956.83  4744.3 1943.07
  4759.4 1937.09  4764.6 1931.86  4774.8 1926.93  4805.3 1913.88  4812.3 1908.62
  4815.4 1909.21  4865.2 1893.21  4870.3 1894.85  4886.6 1891.65  4985.8 1890.84
  5006.7 1888.92  5014.5 1890.29  5018.9 1888.44  5019.2 1887.94  5023.1 1888.44
  5028.8 1890.16  5035.3 1888.88  5148.8 1897.09  5258.4 1937.71  5263.4 1935.63
  5291.7 1951.34  5309.2 1966.95  5389.5 1977.54  5429.6 1985.35  5478.7 1990.17
#Mann=6,-1,0
  4547.8    0.07       0  4708.0     0.1       0  4815.4   0.035       0
  5018.9   0.035       0  5023.1   0.035       0  5291.7     0.1       0
Bank Sta=5018.9,5023.1
Exp/Cntr=0.3,0.1

Chan Stop Cuts=-1