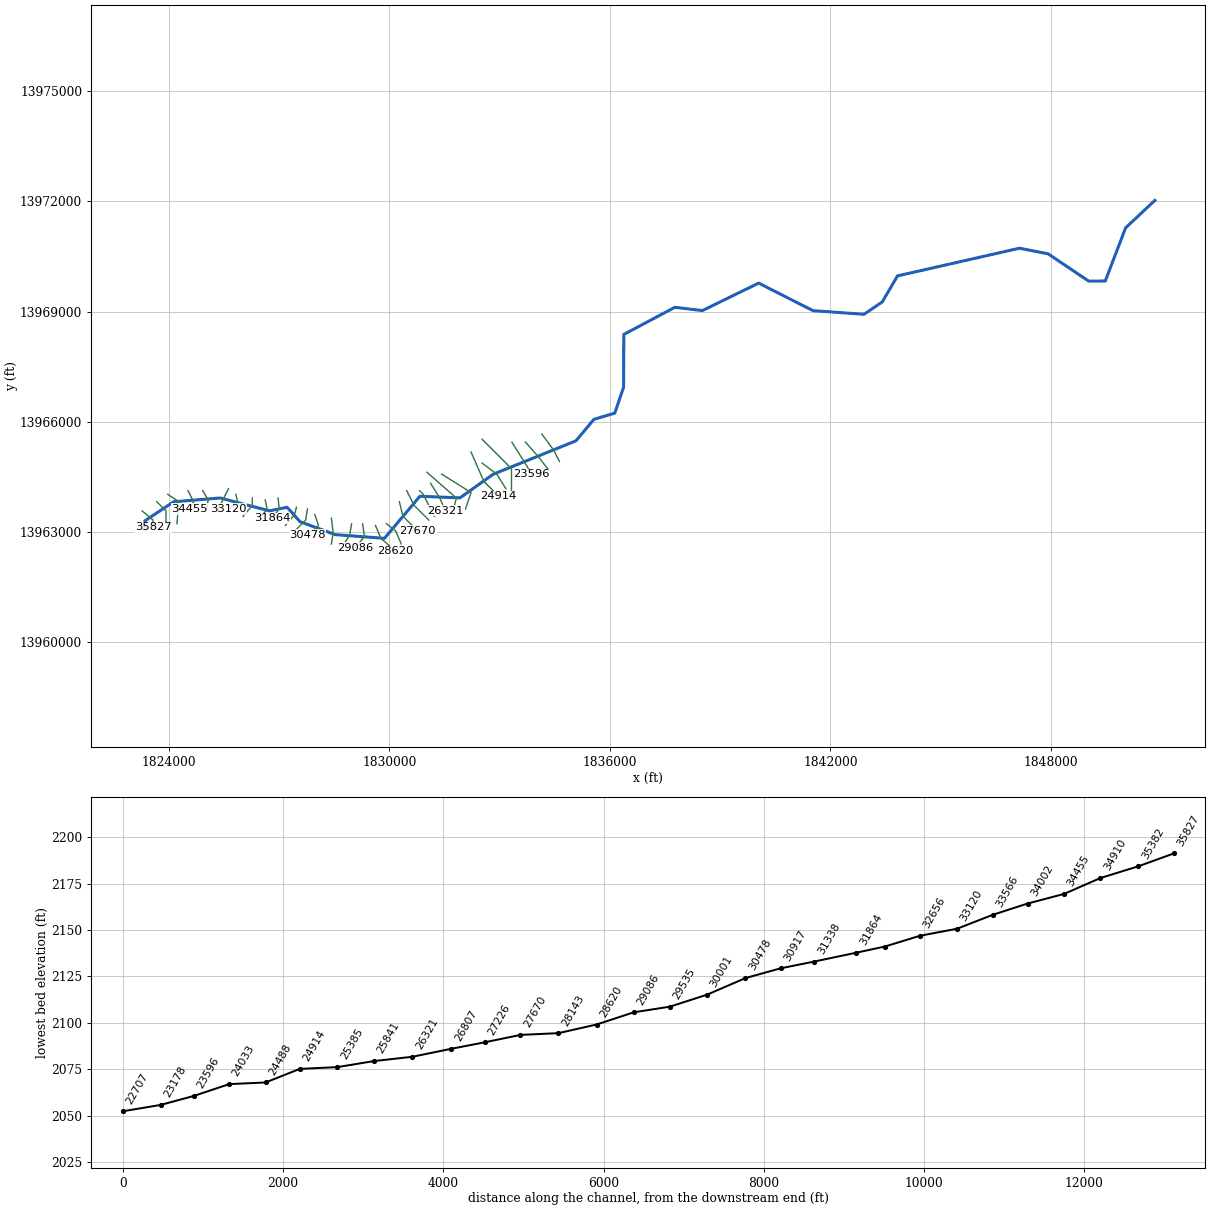
--- Contrary Creek.prj (project) ---

Proj Title=Contrary Creek Base Level Engineering
Current Plan=p01
Default Exp/Contr=0.3,0.1
English Units
Geom File=g01
Flow File=f01
Plan File=p01
Y Axis Title=Elevation
X Axis Title(PF)=Main Channel Distance
X Axis Title(XS)=Station
BEGIN DESCRIPTION:
Contrary Creek
END DESCRIPTION:
DSS Export Rating Curves= 0
DSS Export Rating Curve Sorted= 0
DSS Export Volume Flow Curves= 0
DXF OffsetX= 0
DXF OffsetY= 0
DXF ScaleX= 1
DXF ScaleY= 10

--- Contrary Creek.p01 (plan) ---

Plan Title=Multiple Run
Short Identifier=Multiple
Geom File=g01
Flow File=f01
Subcritical Flow
K Sum by GR= 0
Std Step Tol= 0.01
Critical Tol= 0.01
Num of Std Step Trials= 20
Max Error Tol= 0.3
Flow Tol Ratio= 0.001
Split Flow NTrial= 30
Split Flow Tol= 0.02
Split Flow Ratio= 0.02
Log Output Level= 0
Friction Slope Method= 1
Unsteady Friction Slope Method= 2
Unsteady Bridges Friction Slope Method= 1
Parabolic Critical Depth
Global Vel Dist=  1 , 1 , 1
Global Log Level= 0
CheckData=True
Encroach Param= -1, 0, 0, 0
BEGIN DESCRIPTION:
Multiple Run
END DESCRIPTION:

--- Contrary Creek.f01 (steady flow) ---

Flow Title=Multiple
Number of Profiles=7
Profile Names=10-year,25-year,50-year,1pct_min,100-year,1pct_plu,500-year
River Rch & RM= Contrary Creek,Reach-1,35827
     334     524     690     441     880    1755    1408
River Rch & RM= Contrary Creek,Reach-1,34002
    1075    1823    2529    1694    3380    6743    5967
River Rch & RM= Contrary Creek,Reach-1,30001
    1609    2787    3920    2658    5303   10582    9602
River Rch & RM= Contrary Creek,Reach-1,24914
    2180    3837    5454    3734    7450   14864   13755
River Rch & RM= Contrary Creek,Reach-1,24488
    2775    4946    7092    4893    9763   19480   18316
River Rch & RM= Contrary Creek,Reach-1,23178
    2878    5123    7340    5058   10092   20136   18887
River Rch & RM= Contrary Creek,Reach-1,18589
    3356    6013    8652    5985   11942   23827   22523
River Rch & RM= Contrary Creek,Reach-1,15911
    3593    6453    9299    6442   12853   25645   24307
River Rch & RM= Contrary Creek,Reach-1,12168
    4771    8679   12616    8810   17578   35072   33782
River Rch & RM= Contrary Creek,Reach-1,9276
    5042    9191   13379    9354   18664   37240   35961
River Rch & RM= Contrary Creek,Reach-1,8957
    5465    9990   14568   10202   20355   40614   39342
River Rch & RM= Contrary Creek,Reach-1,4486
    5613   10263   14971   10485   20921   41743   40449
Boundary for River Rch & Prof#=Contrary Creek,Reach-1,1
Up Type=0
Dn Type=3
Dn Slope=0.005
Boundary for River Rch & Prof#=Contrary Creek,Reach-1,2
Up Type=0
Dn Type=3
Dn Slope=0.005
Boundary for River Rch & Prof#=Contrary Creek,Reach-1,3
Up Type=0
Dn Type=3
Dn Slope=0.005
Boundary for River Rch & Prof#=Contrary Creek,Reach-1,4
Up Type=0
Dn Type=3
Dn Slope=0.005
Boundary for River Rch & Prof#=Contrary Creek,Reach-1,5
Up Type=0
Dn Type=3
Dn Slope=0.005
Boundary for River Rch & Prof#=Contrary Creek,Reach-1,6
Up Type=0
Dn Type=3
Dn Slope=0.005
Boundary for River Rch & Prof#=Contrary Creek,Reach-1,7
Up Type=0
Dn Type=3
Dn Slope=0.005

--- Contrary Creek.g01 (geometry) ---

Geom Title=Existing Conditions

River Reach=Contrary Creek,Reach-1
Reach XY= 30
      1823375.00     13963075.00      1823350.97     13963302.35
      1824133.30     13963821.93      1825400.09     13963925.21
      1826740.27     13963575.38      1827219.14     13963672.95
      1827572.70     13963280.09      1828530.93     13962927.24
      1829869.14     13962827.07      1830833.15     13963971.63
      1831923.50     13963928.61      1832826.55     13964571.25
      1835077.55     13965480.73      1835568.94     13966066.86
      1836135.17     13966235.33      1836374.62     13966940.27
      1836380.73     13968377.55      1837768.27     13969115.85
      1838519.06     13969027.25      1840050.08     13969775.20
      1841525.00     13969025.00      1842914.50     13968926.22
      1843411.63     13969261.68      1843826.50     13969971.38
      1847145.03     13970724.94      1847923.50     13970571.39
      1849026.55     13969828.75      1849478.65     13969832.73
      1850030.54     13971277.42      1850825.00     13972025.00

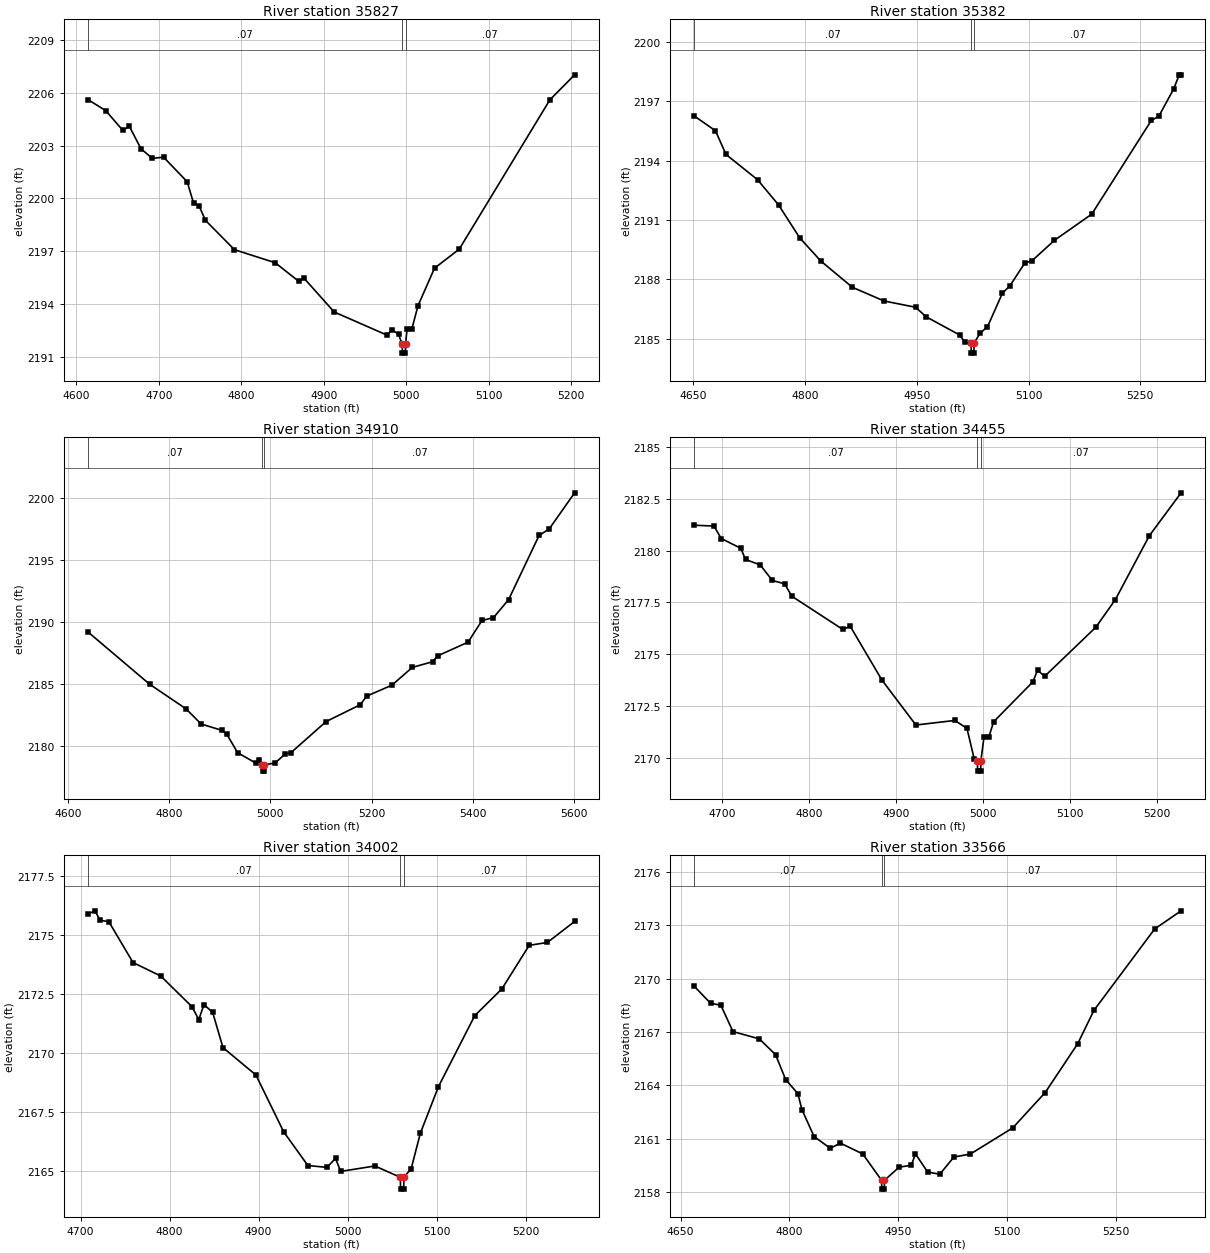
Type RM Length L Ch R = 1,35827,445,445,445
BEGIN DESCRIPTION:
Contrary Creek 75.0
END DESCRIPTION:
XS GIS Cut Line= 3
      1823275.02     13963574.98      1823575.00     13963325.00
      1823575.00     13963124.98
#Sta/Elev= 30
  4614.0 2205.62  4635.4 2205.00  4656.3 2203.87  4664.1 2204.11  4678.4 2202.82
  4692.1 2202.28  4705.7 2202.35  4734.4 2200.95  4742.2 2199.72  4748.7 2199.59
  4756.5 2198.76  4791.7 2197.09  4841.1 2196.35  4869.8 2195.29  4876.3 2195.46
  4912.7 2193.55  4976.5 2192.24  4983.0 2192.54  4990.8 2192.28  4995.3 2191.71
  4995.6 2191.21  4999.1 2191.21  4999.3 2191.71  5001.2 2192.59  5007.0 2192.59
  5014.5 2193.91  5034.5 2196.04  5064.5 2197.12  5174.5 2205.61  5204.5 2207.03
#Mann=3,-1,0
  4614.0    0.07       0  4995.3    0.05       0  4999.3    0.07       0
Bank Sta=4995.3,4999.3
Exp/Cntr=0.3,0.1

Type RM Length L Ch R = 1,35382,472,472,472
BEGIN DESCRIPTION:
Contrary Creek 74.0
END DESCRIPTION:
XS GIS Cut Line= 3
      1823675.03     13963824.97      1823925.00     13963575.00
      1823925.00     13963275.01
#Sta/Elev= 30
  4651.3 2196.25  4679.5 2195.51  4693.7 2194.31  4736.1 2193.03  4764.4 2191.75
  4792.7 2190.09  4821.0 2188.92  4863.4 2187.59  4905.8 2186.90  4948.2 2186.58
  4962.4 2186.10  5007.3 2185.18  5014.8 2184.80  5022.8 2184.76  5023.1 2184.26
  5026.6 2184.26  5026.8 2184.76  5034.8 2185.27  5044.8 2185.59  5064.8 2187.29
  5074.8 2187.66  5094.8 2188.81  5104.8 2188.94  5134.8 2189.97  5184.8 2191.29
  5264.8 2196.03  5274.8 2196.24  5294.8 2197.62  5302.3 2198.34  5304.8 2198.34
#Mann=3,-1,0
  4651.3    0.07       0  5022.8    0.05       0  5026.8    0.07       0
Bank Sta=5022.8,5026.8
Exp/Cntr=0.3,0.1

Type RM Length L Ch R = 1,34910,455,455,455
BEGIN DESCRIPTION:
Contrary Creek 73.0
END DESCRIPTION:
XS GIS Cut Line= 3
      1823974.98     13964025.01      1824275.00     13963825.00
      1824225.00     13963224.96
#Sta/Elev= 30
  4639.1 2189.18  4760.8 2184.97  4832.9 2182.98  4863.0 2181.75  4905.0 2181.23
  4914.0 2180.91  4935.1 2179.44  4971.1 2178.60  4977.1 2178.82  4984.2 2178.45
  4984.4 2177.95  4987.9 2177.95  4988.2 2178.45  5009.7 2178.62  5029.8 2179.36
  5039.8 2179.41  5110.1 2181.95  5177.8 2183.31  5190.3 2184.00  5240.5 2184.89
  5280.6 2186.32  5320.8 2186.78  5330.8 2187.25  5391.0 2188.36  5418.6 2190.11
  5441.2 2190.33  5471.3 2191.80  5531.5 2196.97  5551.6 2197.50  5601.8 2200.41
#Mann=3,-1,0
  4639.1    0.07       0  4984.2    0.05       0  4988.2    0.07       0
Bank Sta=4984.2,4988.2
Exp/Cntr=0.3,0.1

Type RM Length L Ch R = 1,34455,453,453,453
BEGIN DESCRIPTION:
Contrary Creek 72.0
END DESCRIPTION:
XS GIS Cut Line= 3
      1824524.98     13964125.04      1824675.00     13963825.00
      1824574.98     13963624.97
#Sta/Elev= 30
  4668.6 2181.22  4691.0 2181.18  4699.4 2180.58  4721.8 2180.11  4727.3 2179.57
  4744.1 2179.31  4758.1 2178.56  4772.1 2178.40  4780.5 2177.80  4839.1 2176.20
  4847.5 2176.36  4883.9 2173.77  4923.0 2171.60  4967.7 2171.82  4981.7 2171.44
  4990.1 2169.95  4993.7 2169.88  4993.9 2169.38  4997.4 2169.38  4997.7 2169.88
  5001.3 2171.04  5006.9 2171.04  5012.4 2171.76  5057.2 2173.67  5062.8 2174.23
  5071.1 2173.95  5129.8 2176.31  5152.2 2177.64  5191.3 2180.72  5227.7 2182.78
#Mann=3,-1,0
  4668.6    0.07       0  4993.7    0.05       0  4997.7    0.07       0
Bank Sta=4993.7,4997.7
Exp/Cntr=0.3,0.1

Type RM Length L Ch R = 1,34002,436,436,436
BEGIN DESCRIPTION:
Contrary Creek 71.0
END DESCRIPTION:
XS GIS Cut Line= 3
      1824924.99     13964125.02      1825075.00     13963875.00
      1825025.01     13963625.03
#Sta/Elev= 30
  4708.4 2175.88  4716.2 2176.01  4722.0 2175.61  4731.8 2175.55  4759.0 2173.82
  4790.1 2173.25  4825.0 2171.96  4832.8 2171.41  4838.7 2172.04  4848.4 2171.71
  4860.0 2170.22  4897.0 2169.06  4928.1 2166.66  4955.3 2165.23  4976.7 2165.15
  4986.4 2165.53  4992.2 2164.98  5030.6 2165.21  5059.2 2164.73  5059.4 2164.23
  5062.9 2164.23  5063.2 2164.73  5071.4 2165.10  5081.6 2166.59  5102.0 2168.57
  5142.7 2171.57  5173.3 2172.71  5203.9 2174.55  5224.3 2174.67  5254.9 2175.56
#Mann=3,-1,0
  4708.4    0.07       0  5059.2    0.05       0  5063.2    0.07       0
Bank Sta=5059.2,5063.2
Exp/Cntr=0.3,0.1

Type RM Length L Ch R = 1,33566,446,446,446
BEGIN DESCRIPTION:
Contrary Creek 70.0
END DESCRIPTION:
XS GIS Cut Line= 3
      1825624.98     13964174.96      1825475.00     13963875.00
      1825324.99     13963574.98
#Sta/Elev= 30
  4669.2 2169.56  4691.5 2168.61  4705.5 2168.51  4722.3 2167.02  4758.6 2166.61
  4781.0 2165.72  4794.9 2164.32  4811.7 2163.53  4817.3 2162.63  4834.1 2161.11
  4856.4 2160.45  4870.4 2160.74  4901.2 2160.13  4927.1 2158.65  4927.4 2158.15
  4930.9 2158.15  4931.1 2158.65  4951.5 2159.39  4968.2 2159.49  4973.8 2160.14
  4990.6 2159.11  5007.4 2158.99  5026.9 2159.96  5049.3 2160.12  5108.0 2161.60
  5152.7 2163.59  5197.4 2166.33  5219.8 2168.21  5303.6 2172.80  5340.0 2173.82
#Mann=3,-1,0
  4669.2    0.07       0  4927.1    0.05       0  4931.1    0.07       0
Bank Sta=4927.1,4931.1
Exp/Cntr=0.3,0.1

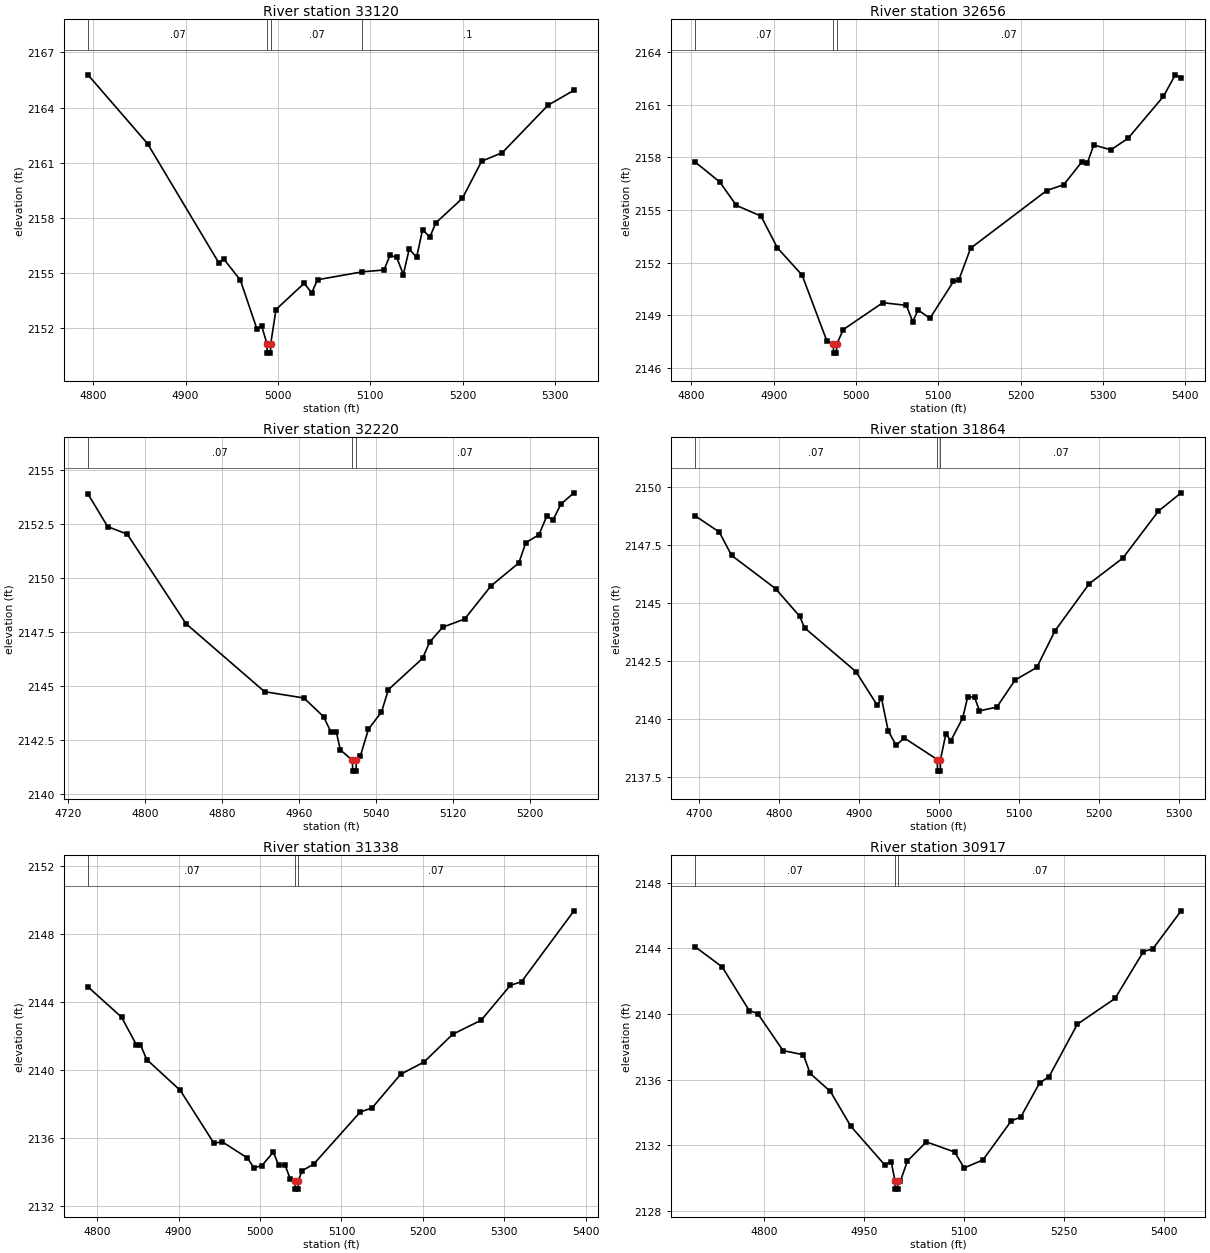
Type RM Length L Ch R = 1,33120,464,464,464
BEGIN DESCRIPTION:
Contrary Creek 69.0
END DESCRIPTION:
XS GIS Cut Line= 3
      1825824.99     13964025.03      1825875.00     13963825.00
      1825625.04     13963625.03
#Sta/Elev= 30
  4794.3 2165.78  4858.8 2162.04  4936.1 2155.55  4941.2 2155.78  4959.3 2154.62
  4977.3 2151.96  4982.5 2152.11  4988.2 2151.15  4988.4 2150.65  4991.9 2150.65
  4992.2 2151.15  4997.9 2153.02  5028.5 2154.45  5036.5 2153.92  5042.9 2154.64
  5091.3 2155.07  5114.9 2155.17  5121.3 2155.96  5128.6 2155.86  5135.8 2154.92
  5142.2 2156.31  5150.2 2155.86  5156.6 2157.35  5164.6 2156.97  5171.0 2157.73
  5199.8 2159.07  5220.6 2161.08  5243.0 2161.55  5292.6 2164.13  5320.6 2164.94
#Mann=4,-1,0
  4794.3    0.07       0  4988.2    0.05       0  4992.2    0.07       0
  5091.3     0.1       0
Bank Sta=4988.2,4992.2
Exp/Cntr=0.3,0.1

Type RM Length L Ch R = 1,32656,436,436,436
BEGIN DESCRIPTION:
Contrary Creek 68.0
END DESCRIPTION:
XS GIS Cut Line= 3
      1826275.00     13963925.00      1826275.00     13963725.00
      1826025.01     13963425.01
#Sta/Elev= 30
  4804.6 2157.73  4834.6 2156.59  4854.6 2155.26  4884.6 2154.65  4904.6 2152.84
  4934.6 2151.29  4964.6 2147.55  4972.6 2147.35  4972.8 2146.85  4976.3 2146.85
  4976.6 2147.35  4984.6 2148.19  5032.6 2149.72  5061.2 2149.57  5069.0 2148.64
  5075.5 2149.31  5089.9 2148.83  5118.5 2150.93  5125.0 2151.01  5139.3 2152.82
  5231.7 2156.10  5252.6 2156.44  5274.7 2157.75  5281.2 2157.68  5289.0 2158.70
  5309.8 2158.42  5330.7 2159.08  5373.6 2161.46  5388.0 2162.69  5395.1 2162.53
#Mann=3,-1,0
  4804.6    0.07       0  4972.6    0.05       0  4976.6    0.07       0
Bank Sta=4972.6,4976.6
Exp/Cntr=0.3,0.1

Type RM Length L Ch R = 1,32220,356,356,356
BEGIN DESCRIPTION:
Contrary Creek 67.0
END DESCRIPTION:
XS GIS Cut Line= 3
      1826625.01     13963874.96      1826675.00     13963625.00
      1826525.01     13963425.01
#Sta/Elev= 30
  4740.7 2153.89  4761.1 2152.38  4781.5 2152.03  4842.6 2147.89  4924.2 2144.75
  4965.0 2144.46  4985.4 2143.60  4993.1 2142.89  4998.7 2142.89  5002.9 2142.06
  5015.5 2141.58  5015.7 2141.08  5019.2 2141.08  5019.5 2141.58  5023.7 2141.78
  5032.1 2143.02  5045.6 2143.81  5052.9 2144.85  5088.3 2146.29  5095.6 2147.04
  5109.2 2147.73  5132.1 2148.11  5159.2 2149.63  5188.3 2150.70  5195.6 2151.64
  5209.2 2152.00  5217.5 2152.88  5223.7 2152.68  5232.1 2153.42  5245.6 2153.94
#Mann=3,-1,0
  4740.7    0.07       0  5015.5    0.05       0  5019.5    0.07       0
Bank Sta=5015.5,5019.5
Exp/Cntr=0.3,0.1

Type RM Length L Ch R = 1,31864,526,526,526
BEGIN DESCRIPTION:
Contrary Creek 66.0
END DESCRIPTION:
XS GIS Cut Line= 3
      1826975.00     13963925.04      1827006.34     13963638.64
      1826825.00     13963374.99
#Sta/Elev= 30
  4695.0 2148.77  4725.2 2148.07  4740.7 2147.06  4795.6 2145.63  4825.8 2144.44
  4831.9 2143.94  4896.2 2142.05  4923.1 2140.59  4928.1 2140.92  4936.5 2139.51
  4946.5 2138.87  4956.6 2139.19  4998.0 2138.26  4998.3 2137.76  5001.8 2137.76
  5002.0 2138.26  5008.8 2139.37  5014.9 2139.07  5029.8 2140.05  5036.1 2140.97
  5044.7 2140.94  5050.8 2140.36  5072.5 2140.52  5095.4 2141.69  5122.5 2142.23
  5145.3 2143.81  5188.1 2145.84  5230.3 2146.95  5274.7 2148.97  5303.1 2149.76
#Mann=3,-1,0
  4695.0    0.07       0  4998.0    0.05       0  5002.0    0.07       0
Bank Sta=4998,5002
Exp/Cntr=0.3,0.1

Type RM Length L Ch R = 1,31338,421,421,421
BEGIN DESCRIPTION:
Contrary Creek 65.0
END DESCRIPTION:
XS GIS Cut Line= 3
      1827475.00     13963674.98      1827425.00     13963475.00
      1827175.03     13963175.04
#Sta/Elev= 30
  4788.8 2144.88  4830.0 2143.10  4848.1 2141.49  4853.2 2141.48  4860.9 2140.61
  4902.2 2138.79  4943.4 2135.69  4953.7 2135.77  4984.6 2134.82  4992.4 2134.25
  5002.1 2134.36  5016.4 2135.17  5022.9 2134.38  5030.7 2134.41  5037.2 2133.58
  5043.1 2133.49  5043.3 2132.99  5046.8 2132.99  5047.1 2133.49  5051.6 2134.07
  5065.9 2134.46  5123.2 2137.53  5137.5 2137.76  5172.6 2139.74  5201.3 2140.46
  5236.4 2142.09  5271.5 2142.92  5307.3 2144.97  5321.0 2145.18  5385.4 2149.35
#Mann=3,-1,0
  4788.8    0.07       0  5043.1    0.05       0  5047.1    0.07       0
Bank Sta=5043.1,5047.1
Exp/Cntr=0.3,0.1

Type RM Length L Ch R = 1,30917,439,439,439
BEGIN DESCRIPTION:
Contrary Creek 64.0
END DESCRIPTION:
XS GIS Cut Line= 3
      1827775.00     13963625.02      1827725.00     13963325.00
      1827425.01     13963025.01
#Sta/Elev= 30
  4696.7 2144.10  4737.3 2142.87  4777.8 2140.21  4790.5 2140.03  4828.5 2137.77
  4858.9 2137.52  4869.1 2136.38  4899.5 2135.28  4929.9 2133.17  4980.6 2130.82
  4990.7 2130.97  4996.3 2129.83  4996.6 2129.33  5000.1 2129.33  5000.3 2129.83
  5004.4 2129.83  5015.0 2131.05  5043.3 2132.21  5085.7 2131.59  5099.9 2130.62
  5128.1 2131.11  5170.6 2133.49  5184.7 2133.72  5213.0 2135.80  5227.1 2136.18
  5269.6 2139.38  5326.1 2140.95  5368.6 2143.81  5382.7 2143.97  5425.1 2146.29
#Mann=3,-1,0
  4696.7    0.07       0  4996.3    0.05       0  5000.3    0.07       0
Bank Sta=4996.3,5000.3
Exp/Cntr=0.3,0.1

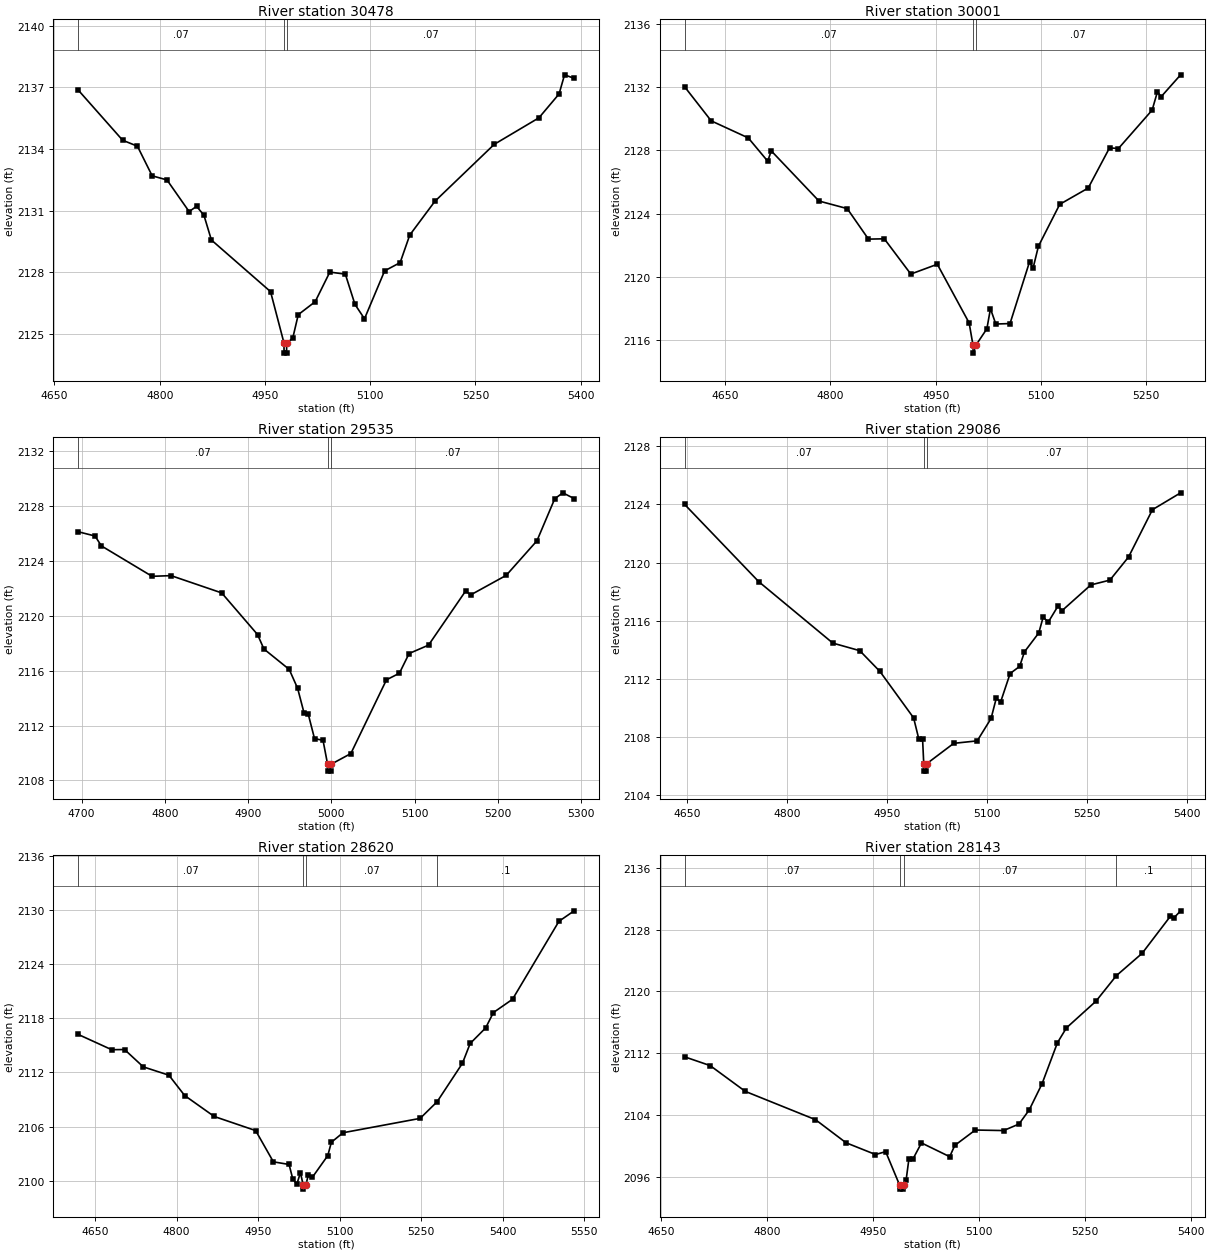
Type RM Length L Ch R = 1,30478,477,477,477
BEGIN DESCRIPTION:
Contrary Creek 63.0
END DESCRIPTION:
XS GIS Cut Line= 3
      1827974.99     13963475.02      1828075.00     13963175.00
      1827774.97     13962924.98
#Sta/Elev= 30
  4683.8 2136.87  4747.1 2134.43  4768.2 2134.14  4789.2 2132.70  4810.3 2132.50
  4841.9 2130.96  4852.5 2131.22  4863.0 2130.78  4873.6 2129.58  4957.9 2127.07
  4977.0 2124.58  4977.2 2124.08  4980.7 2124.08  4981.0 2124.58  4989.5 2124.80
  4997.4 2125.95  5021.5 2126.58  5042.4 2128.02  5064.5 2127.92  5078.2 2126.45
  5091.8 2125.75  5120.5 2128.08  5142.6 2128.48  5156.3 2129.82  5192.1 2131.46
  5276.7 2134.23  5340.4 2135.52  5369.1 2136.68  5376.9 2137.61  5390.6 2137.44
#Mann=3,-1,0
  4683.8    0.07       0  4977.0    0.05       0  4981.0    0.07       0
Bank Sta=4977,4981
Exp/Cntr=0.3,0.1

Type RM Length L Ch R = 1,30001,466,466,466
BEGIN DESCRIPTION:
Contrary Creek 62.0
END DESCRIPTION:
XS GIS Cut Line= 3
      1828425.00     13963375.03      1828475.00     13962975.00
      1828425.00     13962674.98
#Sta/Elev= 30
  4592.1 2132.01  4629.9 2129.86  4682.8 2128.78  4710.5 2127.31  4715.6 2127.96
  4783.6 2124.79  4823.9 2124.31  4854.2 2122.38  4876.8 2122.40  4914.6 2120.17
  4952.4 2120.79  4997.8 2117.08  5003.3 2115.67  5003.6 2115.17  5007.4 2115.67
  5023.1 2116.71  5028.2 2117.98  5035.8 2117.01  5056.1 2117.04  5083.9 2120.94
  5089.0 2120.55  5096.6 2121.93  5127.0 2124.58  5167.6 2125.61  5198.0 2128.15
  5210.7 2128.11  5258.8 2130.54  5266.4 2131.71  5271.5 2131.38  5299.4 2132.77
#Mann=3,-1,0
  4592.1    0.07       0  5003.3    0.05       0  5007.4    0.07       0
Bank Sta=5003.3,5007.4
Exp/Cntr=0.3,0.1

Type RM Length L Ch R = 1,29535,449,449,449
BEGIN DESCRIPTION:
Contrary Creek 61.0
END DESCRIPTION:
XS GIS Cut Line= 3
      1828974.99     13963224.96      1828925.00     13962925.00
      1828775.02     13962675.04
#Sta/Elev= 30
  4696.0 2126.14  4716.2 2125.83  4723.8 2125.11  4784.7 2122.89  4807.5 2122.94
  4868.3 2121.68  4911.4 2118.64  4919.0 2117.59  4949.4 2116.10  4959.5 2114.72
  4967.1 2112.95  4972.2 2112.85  4979.8 2111.05  4990.0 2110.93  4995.5 2109.18
  4995.8 2108.68  4999.4 2108.68  4999.6 2109.18  5023.4 2109.96  5066.2 2115.34
  5081.7 2115.82  5093.4 2117.26  5116.7 2117.87  5161.4 2121.83  5167.2 2121.53
  5210.0 2122.96  5246.9 2125.48  5268.3 2128.55  5278.0 2128.98  5291.6 2128.56
#Mann=3,-1,0
  4696.0    0.07       0  4995.5    0.05       0  4999.6    0.07       0
Bank Sta=4995.5,4999.6
Exp/Cntr=0.3,0.1

Type RM Length L Ch R = 1,29086,466,466,466
BEGIN DESCRIPTION:
Contrary Creek 60.0
END DESCRIPTION:
XS GIS Cut Line= 3
      1829274.99     13963225.04      1829325.00     13962875.00
      1829075.01     13962575.01
#Sta/Elev= 30
  4646.5 2124.00  4757.7 2118.69  4868.8 2114.47  4909.2 2113.95  4939.5 2112.52
  4990.0 2109.33  4997.6 2107.91  5003.4 2107.91  5005.2 2106.17  5005.5 2105.67
  5009.1 2105.67  5009.4 2106.17  5050.2 2107.58  5085.4 2107.75  5106.2 2109.29
  5114.0 2110.68  5120.5 2110.42  5134.8 2112.38  5149.1 2112.87  5156.3 2113.87
  5177.8 2115.17  5184.3 2116.25  5192.1 2115.92  5206.4 2117.00  5212.9 2116.71
  5255.9 2118.47  5284.5 2118.80  5312.5 2120.39  5348.3 2123.64  5390.6 2124.80
#Mann=3,-1,0
  4646.5    0.07       0  5005.2    0.05       0  5009.4    0.07       0
Bank Sta=5005.2,5009.4
Exp/Cntr=0.3,0.1

Type RM Length L Ch R = 1,28620,477,477,477
BEGIN DESCRIPTION:
Contrary Creek 59.0
END DESCRIPTION:
XS GIS Cut Line= 3
      1829625.00     13963174.99      1829775.00     13962825.00
      1830175.01     13962474.99
#Sta/Elev= 30
  4619.1 2116.20  4680.7 2114.51  4704.3 2114.53  4738.8 2112.61  4785.9 2111.69
  4814.9 2109.44  4869.3 2107.12  4945.5 2105.56  4978.1 2102.10  5007.0 2101.81
  5013.6 2100.25  5021.2 2099.62  5027.9 2100.90  5032.8 2099.58  5033.2 2099.08
  5038.1 2099.58  5042.1 2100.59  5049.7 2100.38  5078.2 2102.79  5084.8 2104.27
  5106.2 2105.32  5248.1 2106.91  5279.3 2108.75  5325.9 2113.01  5340.1 2115.20
  5368.6 2116.92  5382.8 2118.62  5418.0 2120.09  5503.4 2128.72  5531.4 2129.88
#Mann=4,-1,0
  4619.1    0.07       0  5032.8    0.05       0  5038.1    0.07       0
  5279.3     0.1       0
Bank Sta=5032.8,5038.1
Exp/Cntr=0.3,0.1

Type RM Length L Ch R = 1,28143,473,473,473
BEGIN DESCRIPTION:
Contrary Creek 58.0
END DESCRIPTION:
XS GIS Cut Line= 3
      1829924.99     13963225.01      1830175.00     13963025.00
      1830325.02     13962674.96
#Sta/Elev= 30
  4683.9 2111.54  4719.9 2110.41  4769.6 2107.07  4868.8 2103.41  4912.0 2100.42
  4953.6 2098.90  4968.0 2099.27  4987.8 2094.92  4988.2 2094.42  4992.7 2094.42
  4993.2 2094.92  4996.9 2095.60  5000.9 2098.36  5006.8 2098.36  5018.6 2100.40
  5058.5 2098.62  5065.7 2100.08  5094.7 2102.07  5134.6 2102.00  5156.4 2102.84
  5170.9 2104.67  5189.0 2108.05  5210.8 2113.37  5223.5 2115.29  5265.2 2118.74
  5294.0 2122.04  5330.5 2124.94  5370.3 2129.72  5375.8 2129.56  5384.9 2130.44
#Mann=4,-1,0
  4683.9    0.07       0  4987.8    0.05       0  4993.2    0.07       0
  5294.0     0.1       0
Bank Sta=4987.8,4993.2
Exp/Cntr=0.3,0.1

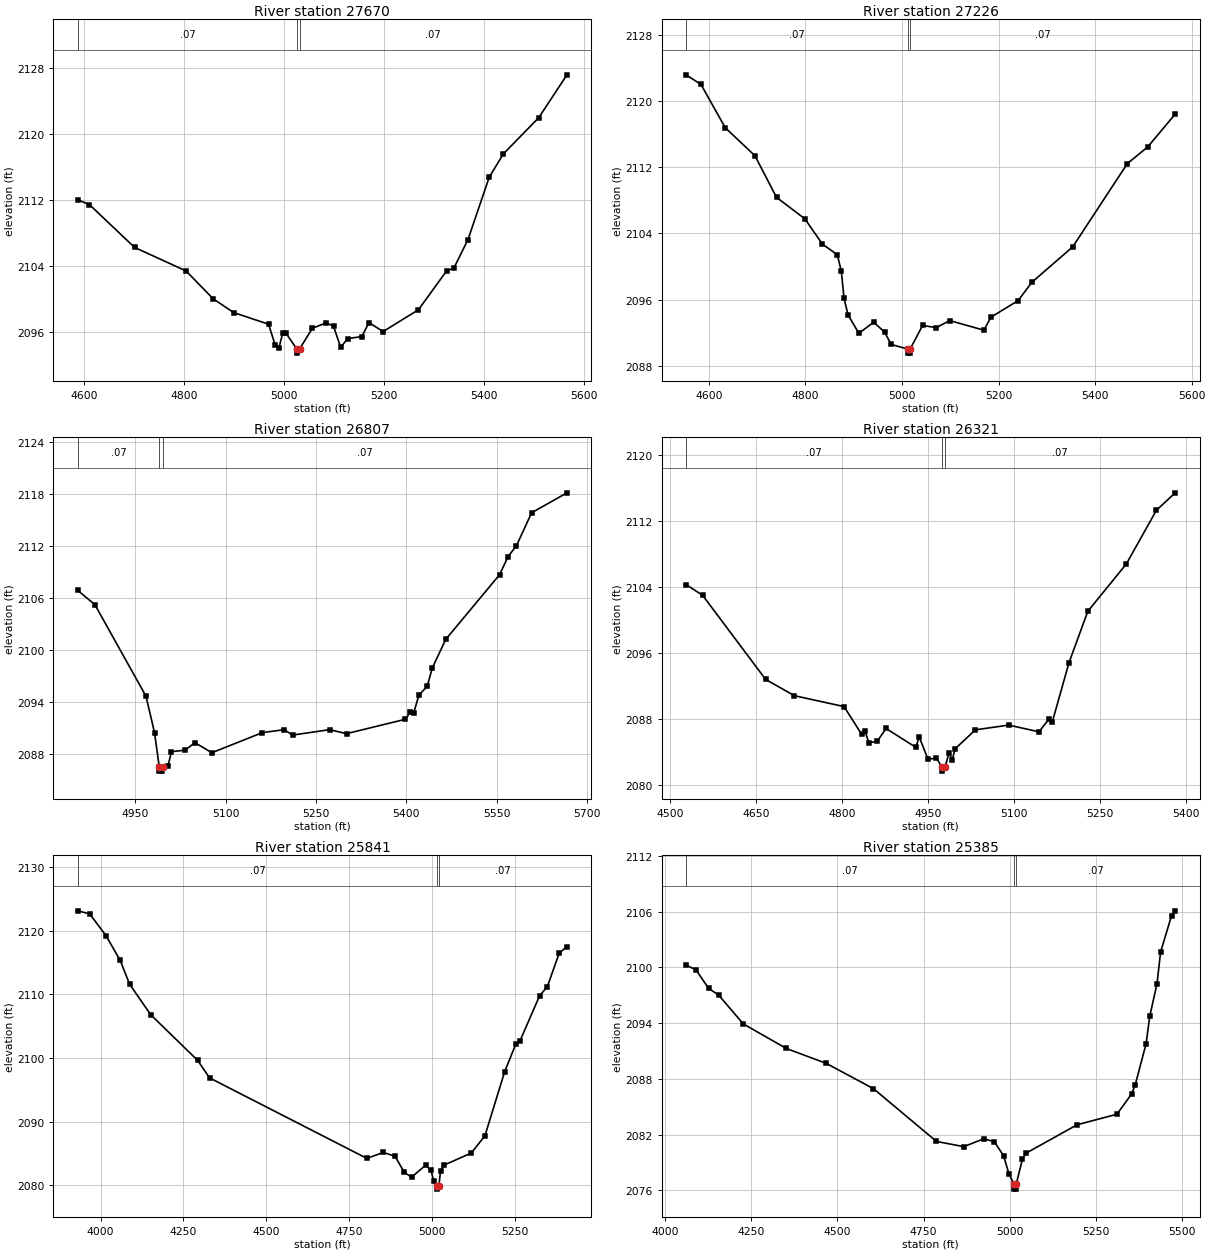
Type RM Length L Ch R = 1,27670,444,444,444
BEGIN DESCRIPTION:
Contrary Creek 57.0
END DESCRIPTION:
XS GIS Cut Line= 3
      1830275.01     13963824.95      1830375.00     13963425.00
      1830774.97     13963025.03
#Sta/Elev= 30
  4588.0 2112.04  4611.1 2111.46  4701.3 2106.28  4804.4 2103.43  4858.5 2100.06
  4899.8 2098.39  4969.3 2096.99  4982.2 2094.52  4990.0 2094.14  4997.7 2095.92
  5003.8 2095.92  5025.8 2093.99  5026.2 2093.49  5031.3 2093.99  5056.8 2096.49
  5085.1 2097.17  5099.3 2096.73  5113.4 2094.19  5127.5 2095.25  5155.8 2095.49
  5170.0 2097.19  5198.3 2096.10  5269.0 2098.74  5325.5 2103.46  5339.7 2103.76
  5368.0 2107.23  5410.4 2114.76  5438.7 2117.59  5509.4 2121.97  5565.9 2127.16
#Mann=3,-1,0
  4588.0    0.07       0  5025.8    0.05       0  5031.3    0.07       0
Bank Sta=5025.8,5031.3
Exp/Cntr=0.3,0.1

Type RM Length L Ch R = 1,27226,419,419,419
BEGIN DESCRIPTION:
Contrary Creek 56.0
END DESCRIPTION:
XS GIS Cut Line= 3
      1830474.99     13964125.02      1830675.00     13963725.00
      1831074.98     13963325.02
#Sta/Elev= 30
  4553.0 2123.15  4583.8 2121.99  4634.1 2116.76  4695.6 2113.37  4740.3 2108.34
  4799.0 2105.75  4835.3 2102.69  4866.1 2101.42  4874.5 2099.41  4880.1 2096.14
  4888.4 2094.14  4910.8 2091.91  4941.5 2093.26  4963.9 2092.07  4977.9 2090.57
  5011.6 2090.02  5012.0 2089.52  5016.7 2089.52  5017.2 2090.02  5042.7 2092.86
  5071.0 2092.61  5099.2 2093.45  5169.9 2092.29  5184.1 2093.85  5240.7 2095.87
  5268.9 2098.07  5353.8 2102.37  5466.9 2112.43  5509.4 2114.46  5565.9 2118.40
#Mann=3,-1,0
  4553.0    0.07       0  5011.6    0.05       0  5017.2    0.07       0
Bank Sta=5011.6,5017.2
Exp/Cntr=0.3,0.1

Type RM Length L Ch R = 1,26807,486,486,486
BEGIN DESCRIPTION:
Contrary Creek 55.0
END DESCRIPTION:
XS GIS Cut Line= 3
      1830825.01     13964124.99      1830925.00     13964025.00
      1831224.99     13963425.02
#Sta/Elev= 30
  4854.6 2106.85  4882.9 2105.21  4967.7 2094.66  4981.9 2090.46  4989.7 2086.52
  4990.1 2086.02  4994.8 2086.02  4995.3 2086.52  5004.4 2086.65  5010.0 2088.27
  5032.3 2088.43  5049.1 2089.30  5077.1 2088.14  5160.9 2090.46  5197.2 2090.80
  5211.2 2090.18  5272.7 2090.80  5300.7 2090.34  5398.5 2092.00  5406.9 2092.85
  5412.5 2092.78  5420.9 2094.78  5434.8 2095.81  5443.2 2097.92  5465.6 2101.22
  5555.0 2108.68  5569.0 2110.76  5583.0 2112.02  5608.1 2115.81  5666.8 2118.11
#Mann=3,-1,0
  4854.6    0.07       0  4989.7    0.05       0  4995.3    0.07       0
Bank Sta=4989.7,4995.3
Exp/Cntr=0.3,0.1

Type RM Length L Ch R = 1,26321,480,480,480
BEGIN DESCRIPTION:
Contrary Creek 54.0
END DESCRIPTION:
XS GIS Cut Line= 3
      1831125.00     13964325.00      1831375.00     13963925.00
      1831525.00     13963574.99
#Sta/Elev= 30
  4528.3 2104.29  4557.2 2102.98  4666.9 2092.81  4717.0 2090.84  4803.7 2089.52
  4834.3 2086.16  4840.2 2086.57  4846.7 2085.15  4861.4 2085.31  4876.8 2086.87
  4928.7 2084.59  4934.6 2085.85  4949.9 2083.15  4964.6 2083.28  4974.2 2082.21
  4974.6 2081.71  4979.9 2082.21  4986.4 2083.90  4992.3 2083.09  4997.1 2084.40
  5032.6 2086.71  5090.7 2087.28  5143.3 2086.47  5161.4 2088.05  5166.8 2087.71
  5195.8 2094.85  5228.5 2101.05  5295.6 2106.78  5348.2 2113.29  5380.8 2115.39
#Mann=3,-1,0
  4528.3    0.07       0  4974.2    0.05       0  4979.9    0.07       0
Bank Sta=4974.2,4979.9
Exp/Cntr=0.3,0.1

Type RM Length L Ch R = 1,25841,456,456,456
BEGIN DESCRIPTION:
Contrary Creek 53.0
END DESCRIPTION:
XS GIS Cut Line= 3
      1831025.00     13964625.00      1831825.00     13963925.00
      1831725.01     13963525.02
#Sta/Elev= 30
  3931.5 2123.14  3967.1 2122.66  4016.4 2119.23  4059.2 2115.34  4087.6 2111.60
  4151.2 2106.81  4292.6 2099.64  4328.7 2096.88  4803.3 2084.22  4852.6 2085.16
  4888.2 2084.56  4916.2 2082.02  4938.0 2081.27  4980.8 2083.16  4997.1 2082.33
  5004.8 2080.61  5014.9 2079.89  5015.3 2079.39  5020.6 2079.89  5025.4 2082.25
  5035.7 2083.16  5118.2 2085.06  5159.4 2087.78  5218.7 2097.82  5252.2 2102.15
  5265.1 2102.69  5324.4 2109.80  5347.6 2111.21  5383.6 2116.52  5406.8 2117.51
#Mann=3,-1,0
  3931.5    0.07       0  5014.9    0.05       0  5020.6    0.07       0
Bank Sta=5014.9,5020.6
Exp/Cntr=0.3,0.1

Type RM Length L Ch R = 1,25385,471,471,471
BEGIN DESCRIPTION:
Contrary Creek 52.0
END DESCRIPTION:
XS GIS Cut Line= 3
      1831425.04     13964574.98      1832225.00     13964075.00
      1832075.00     13963624.99
#Sta/Elev= 30
  4061.6 2100.24  4090.4 2099.73  4127.0 2097.73  4155.9 2097.02  4227.2 2093.92
  4352.2 2091.27  4467.8 2089.67  4604.6 2086.95  4787.4 2081.27  4866.4 2080.71
  4924.2 2081.55  4954.8 2081.25  4982.0 2079.73  4997.3 2077.79  5012.6 2076.64
  5013.1 2076.14  5017.9 2076.14  5018.3 2076.64  5036.6 2079.38  5047.1 2080.01
  5194.7 2083.06  5310.6 2084.20  5352.8 2086.37  5363.3 2087.33  5395.0 2091.79
  5405.5 2094.72  5426.6 2098.24  5437.1 2101.66  5468.8 2105.56  5479.3 2106.08
#Mann=3,-1,0
  4061.6    0.07       0  5012.6    0.05       0  5018.3    0.07       0
Bank Sta=5012.6,5018.3
Exp/Cntr=0.3,0.1

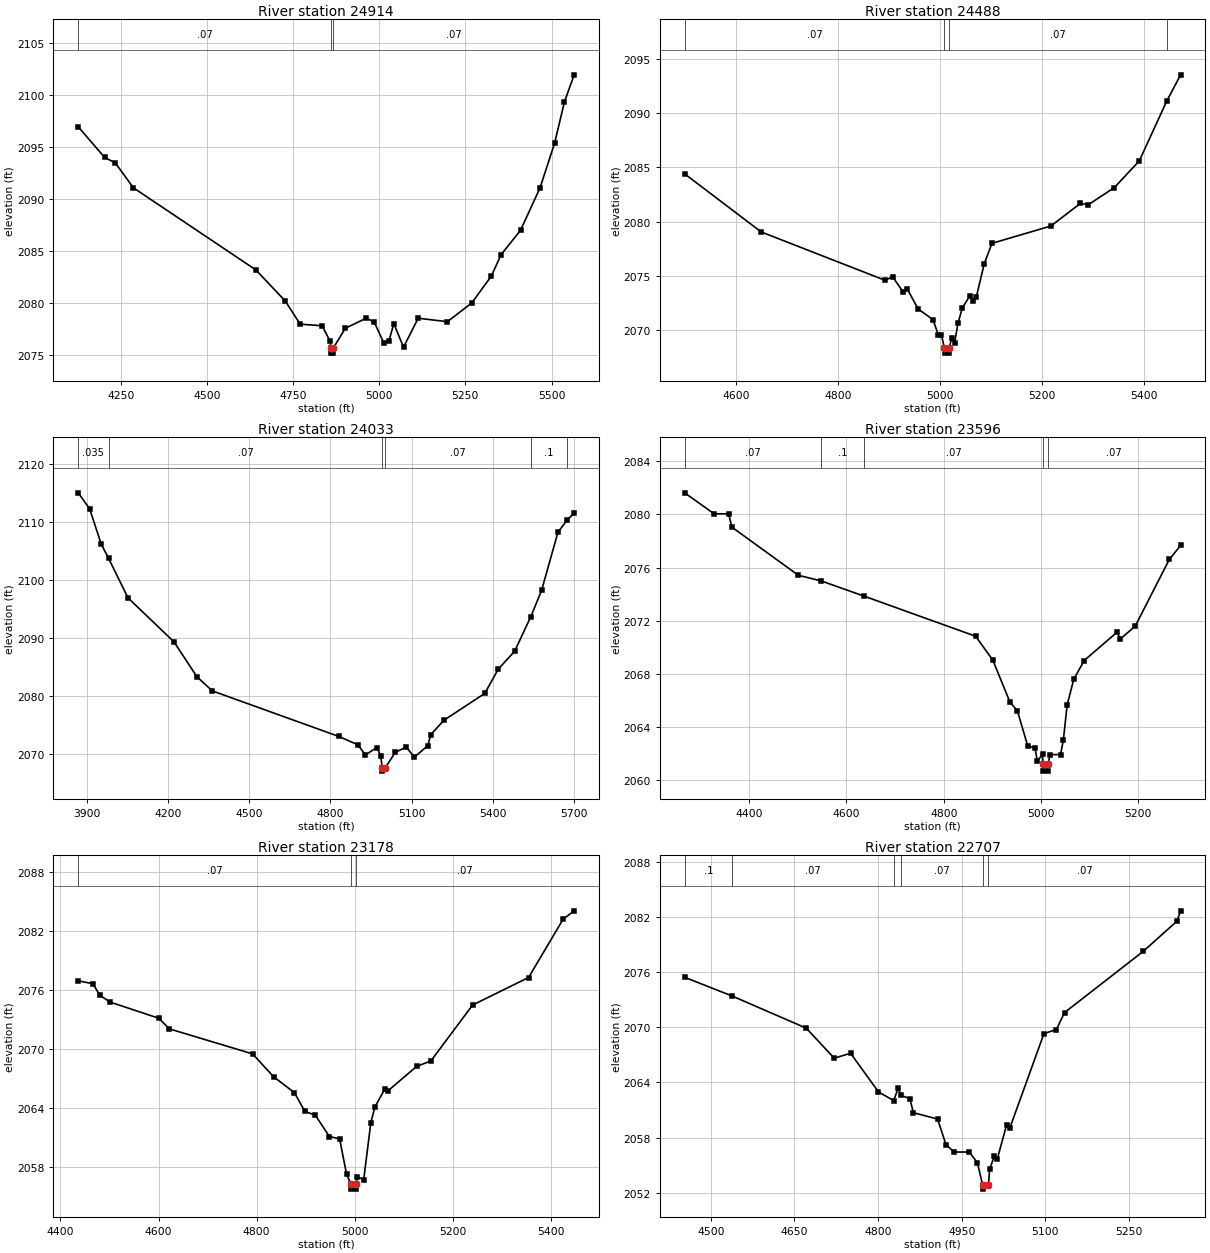
Type RM Length L Ch R = 1,24914,426,426,426
BEGIN DESCRIPTION:
Contrary Creek 51.0
END DESCRIPTION:
XS GIS Cut Line= 3
      1832225.00     13965174.99      1832575.00     13964375.00
      1832975.01     13963974.99
#Sta/Elev= 30
  4126.8 2096.91  4203.2 2093.98  4234.8 2093.43  4287.0 2091.05  4641.8 2083.18
  4727.1 2080.20  4770.8 2077.96  4834.3 2077.81  4857.7 2076.32  4859.2 2075.68
  4859.7 2075.18  4866.7 2075.18  4867.2 2075.68  4901.8 2077.57  4962.2 2078.53
  4985.6 2078.17  5014.1 2076.11  5028.3 2076.34  5042.4 2078.02  5070.7 2075.75
  5113.1 2078.53  5198.0 2078.20  5268.7 2080.00  5325.3 2082.57  5353.6 2084.63
  5410.1 2086.97  5466.7 2091.05  5509.1 2095.35  5537.4 2099.29  5565.7 2101.90
#Mann=3,-1,0
  4126.8    0.07       0  4859.2    0.05       0  4867.2    0.07       0
Bank Sta=4859.2,4867.2
Exp/Cntr=0.3,0.1

Type RM Length L Ch R = 1,24488,455,455,455
BEGIN DESCRIPTION:
Contrary Creek 50.0
END DESCRIPTION:
XS GIS Cut Line= 3
      1832524.98     13964875.01      1832925.00     13964575.00
      1833174.99     13964175.02
#Sta/Elev= 30
  4500.0 2084.41  4650.0 2079.05  4892.7 2074.59  4907.3 2074.92  4928.1 2073.51
  4936.5 2073.76  4957.3 2071.95  4986.5 2070.96  4996.9 2069.57  5003.0 2069.57
  5008.6 2068.37  5009.1 2067.87  5018.1 2067.87  5018.6 2068.37  5023.0 2069.25
  5028.9 2068.79  5035.4 2070.63  5044.2 2072.06  5059.0 2073.17  5065.5 2072.69
  5071.4 2073.04  5086.7 2076.08  5102.0 2078.00  5217.6 2079.60  5275.4 2081.69
  5290.7 2081.56  5342.0 2083.15  5390.9 2085.62  5444.3 2091.11  5471.7 2093.55
#Mann=4,-1,0
  4500.0    0.07       0  5008.6    0.05       0  5018.6    0.07       0
  5444.3     0.1       0
Bank Sta=5008.6,5018.6
Exp/Cntr=0.3,0.1

Type RM Length L Ch R = 1,24033,437,437,437
BEGIN DESCRIPTION:
Contrary Creek 49.0
END DESCRIPTION:
XS GIS Cut Line= 3
      1832525.00     13965525.00      1833325.00     13964725.00
      1833325.00     13964024.97
#Sta/Elev= 30
  3868.9 2115.05  3911.3 2112.28  3953.8 2106.19  3980.8 2103.76  4052.7 2096.91
  4222.5 2089.31  4307.3 2083.28  4363.9 2080.84  4830.6 2072.98  4901.3 2071.54
  4929.6 2069.79  4972.0 2071.06  4986.1 2069.61  4991.7 2067.48  4992.2 2066.98
  5001.8 2067.48  5040.3 2070.25  5080.3 2071.12  5110.3 2069.40  5160.3 2071.40
  5170.3 2073.27  5220.3 2075.79  5370.3 2080.41  5420.3 2084.62  5480.3 2087.67
  5540.5 2093.68  5580.3 2098.23  5640.3 2108.22  5674.4 2110.36  5700.3 2111.54
#Mann=6,-1,0
  3868.9   0.035       0  3980.8    0.07       0  4991.7    0.05       0
  5001.8    0.07       0  5540.5     0.1       0  5674.4    0.07       0
Bank Sta=4991.7,5001.8
Exp/Cntr=0.3,0.1

Type RM Length L Ch R = 1,23596,418,418,418
BEGIN DESCRIPTION:
Contrary Creek 48.0
END DESCRIPTION:
XS GIS Cut Line= 3
      1833338.18     13965441.57      1833725.00     13964825.00
      1833874.99     13964575.01
#Sta/Elev= 30
  4267.5 2081.63  4327.9 2080.05  4357.9 2080.05  4364.4 2079.05  4501.1 2075.42
  4547.7 2075.00  4636.9 2073.84  4865.5 2070.83  4900.9 2069.03  4936.3 2065.85
  4951.2 2065.23  4972.4 2062.60  4987.7 2062.39  4992.4 2061.41  5003.1 2061.96
  5003.8 2061.17  5004.3 2060.67  5013.7 2060.67  5014.2 2061.17  5018.7 2061.91
  5040.1 2061.92  5045.9 2063.02  5053.7 2065.67  5067.3 2067.59  5088.7 2069.00
  5156.7 2071.15  5162.5 2070.61  5193.6 2071.59  5263.6 2076.61  5286.9 2077.67
#Mann=5,-1,0
  4267.5    0.07       0  4547.7     0.1       0  4636.9    0.07       0
  5003.8    0.05       0  5014.2    0.07       0
Bank Sta=5003.8,5014.2
Exp/Cntr=0.3,0.1

Type RM Length L Ch R = 1,23178,471,471,471
BEGIN DESCRIPTION:
Contrary Creek 47.0
END DESCRIPTION:
XS GIS Cut Line= 3
      1833700.07     13965452.18      1834075.00     13965025.00
      1834345.76     13964675.10
#Sta/Elev= 30
  4436.3 2076.96  4466.2 2076.67  4480.4 2075.49  4501.3 2074.80  4600.9 2073.15
  4621.8 2072.08  4791.8 2069.53  4834.4 2067.21  4877.0 2065.59  4898.2 2063.69
  4919.7 2063.29  4948.2 2061.13  4969.1 2060.89  4983.3 2057.28  4992.3 2056.28
  4992.8 2055.78  5002.4 2055.78  5002.9 2056.28  5004.7 2057.03  5018.2 2056.75
  5032.7 2062.54  5040.9 2064.13  5061.7 2066.00  5068.0 2065.79  5126.0 2068.26
  5155.0 2068.81  5240.1 2074.50  5354.2 2077.30  5424.8 2083.24  5447.1 2084.08
#Mann=3,-1,0
  4436.3    0.07       0  4992.3    0.05       0  5002.9    0.07       0
Bank Sta=4992.3,5002.9
Exp/Cntr=0.3,0.1

Type RM Length L Ch R = 1,22707,450,450,450
BEGIN DESCRIPTION:
Contrary Creek 46.0
END DESCRIPTION:
XS GIS Cut Line= 3
      1834149.86     13965664.73      1834475.00     13965225.00
      1834629.58     13964919.24
#Sta/Elev= 30
  4453.1 2075.45  4538.3 2073.41  4671.2 2069.91  4721.3 2066.64  4750.6 2067.18
  4800.7 2062.97  4827.9 2062.02  4836.1 2063.38  4840.8 2062.59  4857.0 2062.24
  4863.2 2060.71  4906.7 2060.01  4921.7 2057.24  4936.3 2056.42  4963.4 2056.42
  4978.0 2055.28  4987.3 2052.88  4987.8 2052.38  4998.0 2052.88  5000.0 2054.52
  5008.3 2055.97  5013.9 2055.69  5030.6 2059.40  5036.2 2059.02  5097.5 2069.32
  5119.8 2069.76  5134.4 2071.61  5275.8 2078.29  5336.1 2081.57  5342.6 2082.69
#Mann=6,-1,0
  4453.1     0.1       0  4538.3    0.07       0  4827.9   0.035       0
  4840.8    0.07       0  4987.3    0.05       0  4998.0    0.07       0
Bank Sta=4987.3,4998
Exp/Cntr=0.3,0.1