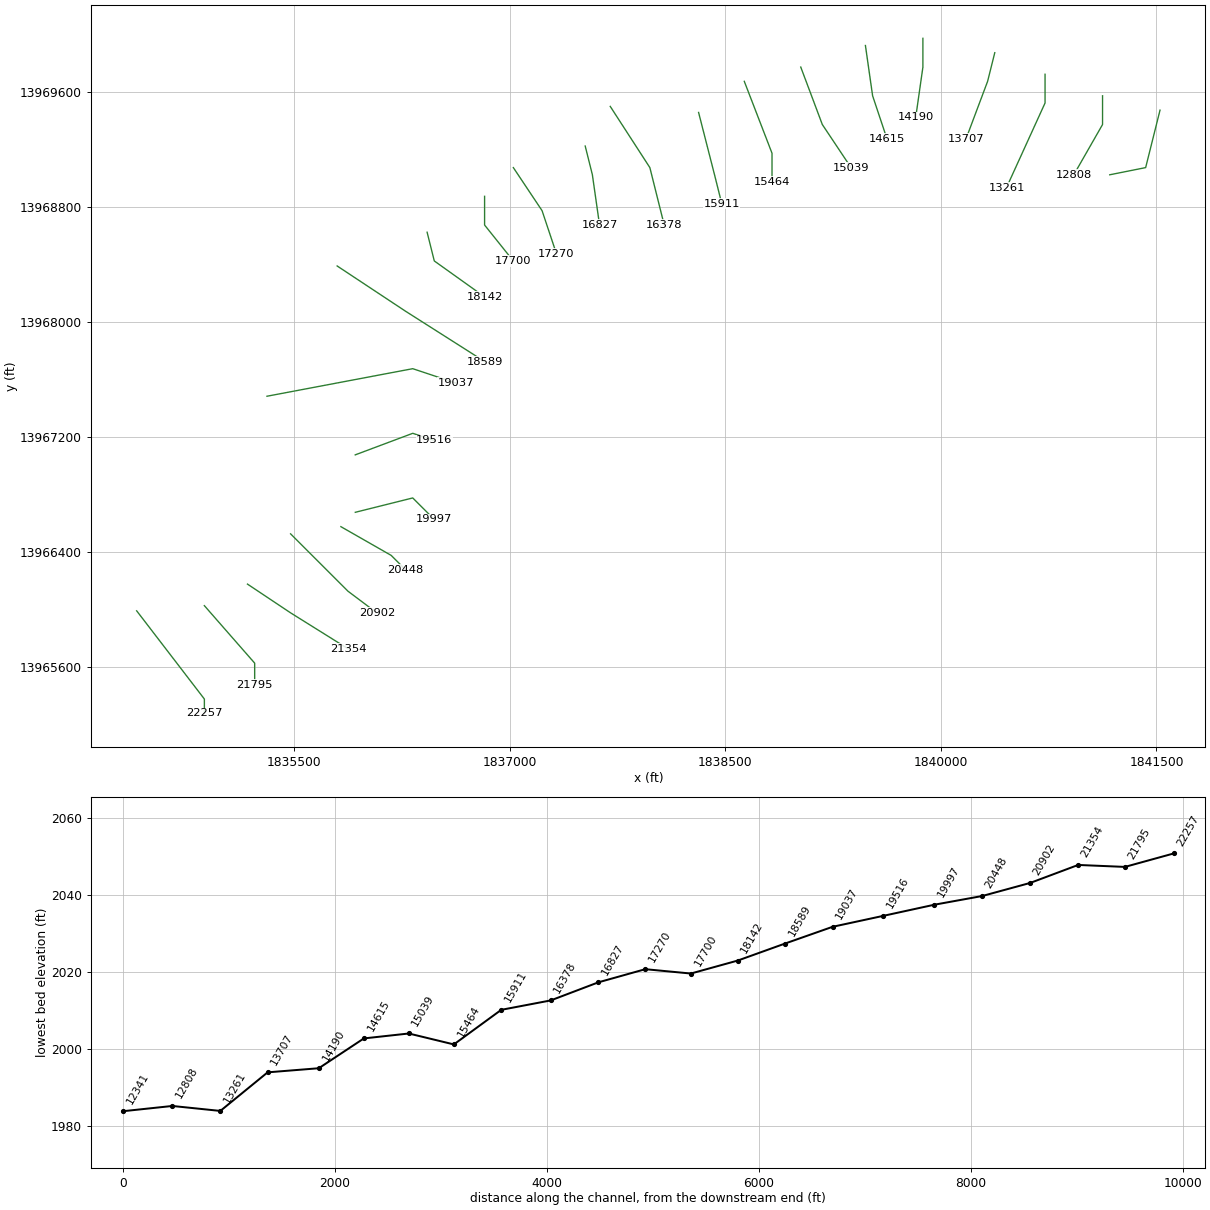
HEC-RAS study Contrary Creek.prj: Contrary Creek Base Level Engineering

--- Contrary Creek.g01 (geometry) --- (continued)

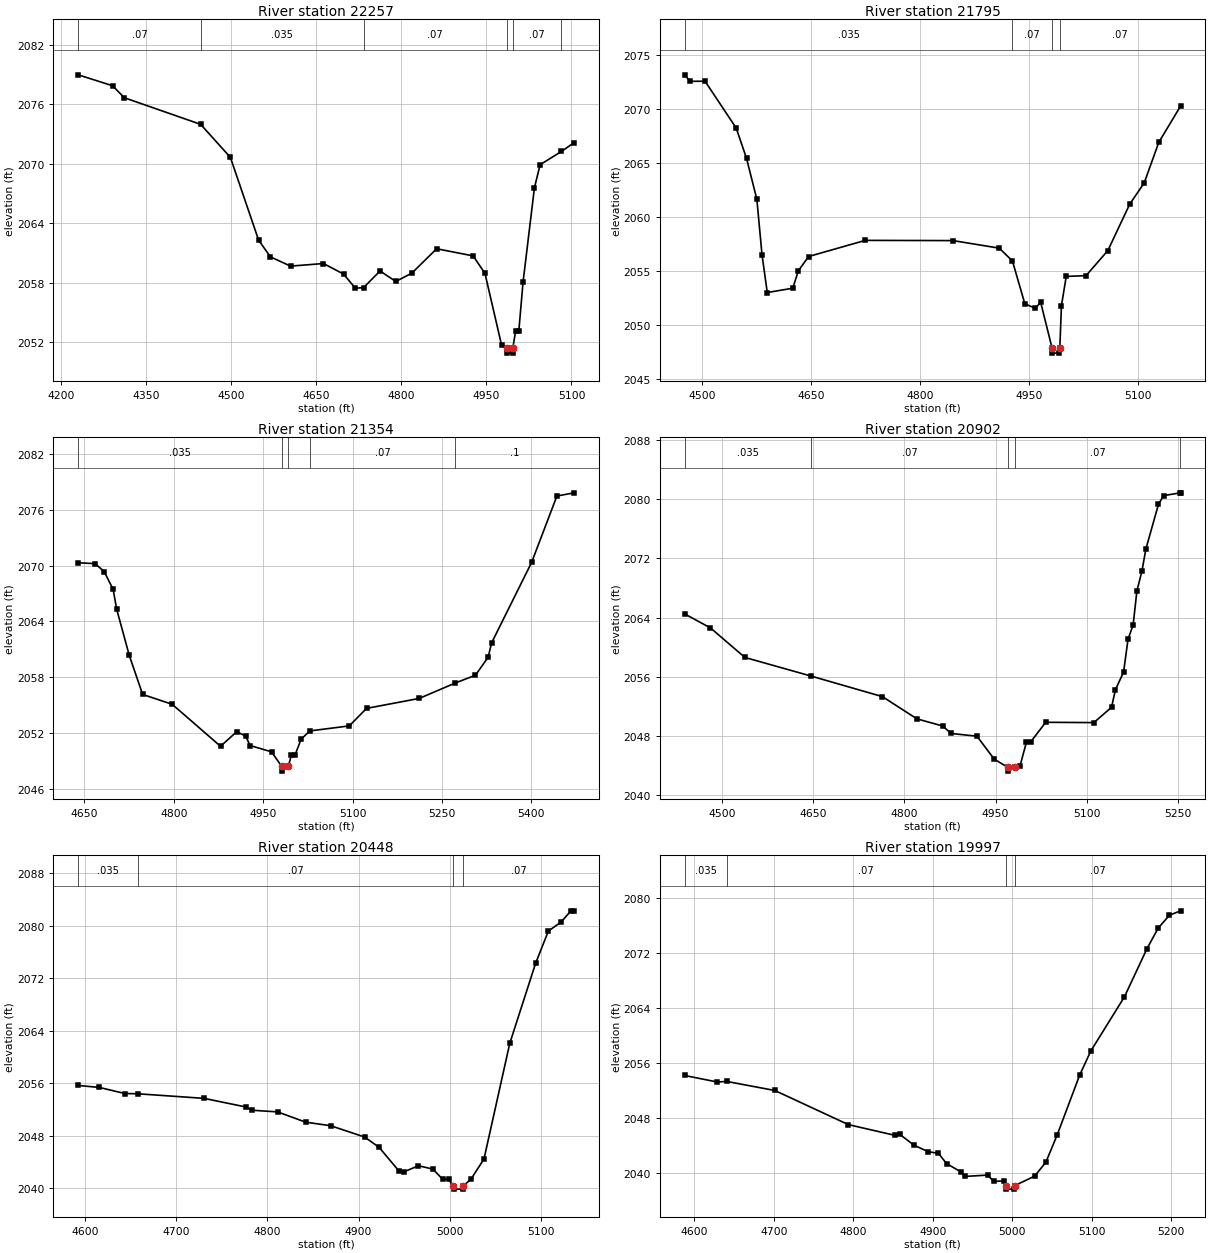
Type RM Length L Ch R = 1,22257,462,462,462
BEGIN DESCRIPTION:
Contrary Creek 45.0
END DESCRIPTION:
XS GIS Cut Line= 3
      1834403.99     13965988.99      1834875.00     13965375.00
      1834875.00     13965275.04
#Sta/Elev= 30
  4230.9 2078.97  4291.4 2077.87  4312.2 2076.66  4446.6 2073.98  4499.0 2070.65
  4548.8 2062.30  4569.6 2060.62  4605.0 2059.69  4663.0 2059.95  4698.4 2058.89
  4719.2 2057.46  4733.8 2057.53  4762.7 2059.20  4790.5 2058.14  4818.9 2058.99
  4862.4 2061.44  4926.8 2060.72  4947.6 2058.95  4976.7 2051.76  4985.8 2051.42
  4986.3 2050.92  4996.1 2050.92  4996.6 2051.42  5001.6 2053.15  5007.2 2053.15
  5014.7 2058.09  5034.7 2067.58  5044.7 2069.91  5082.4 2071.25  5104.7 2072.14
#Mann=6,-1,0
  4230.9    0.07       0  4446.6   0.035       0  4733.8    0.07       0
  4985.8    0.05       0  4996.6    0.07       0  5082.4     0.1       0
Bank Sta=4985.8,4996.6
Exp/Cntr=0.3,0.1

Type RM Length L Ch R = 1,21795,441,441,441
BEGIN DESCRIPTION:
Contrary Creek 44.0
END DESCRIPTION:
XS GIS Cut Line= 3
      1834874.97     13966025.04      1835225.00     13965625.00
      1835225.00     13965474.95
#Sta/Elev= 30
  4476.5 2073.13  4483.7 2072.53  4504.5 2072.54  4547.3 2068.21  4561.5 2065.41
  4575.7 2061.62  4582.8 2056.49  4590.0 2053.01  4625.1 2053.41  4632.7 2055.02
  4646.9 2056.34  4724.7 2057.83  4845.3 2057.81  4908.9 2057.11  4927.0 2055.92
  4944.0 2051.97  4958.2 2051.56  4965.8 2052.10  4981.3 2047.91  4981.8 2047.41
  4991.6 2047.41  4992.1 2047.91  4994.3 2051.79  5000.9 2054.50  5028.1 2054.57
  5058.1 2056.89  5088.1 2061.17  5108.1 2063.15  5128.1 2066.89  5158.1 2070.25
#Mann=4,-1,0
  4476.5   0.035       0  4927.0    0.07       0  4981.3    0.05       0
  4992.1    0.07       0
Bank Sta=4981.3,4992.1
Exp/Cntr=0.3,0.1

Type RM Length L Ch R = 1,21354,452,452,452
BEGIN DESCRIPTION:
Contrary Creek 43.0
END DESCRIPTION:
XS GIS Cut Line= 3
      1835175.02     13966174.99      1835475.00     13965975.00
      1835874.97     13965725.02
#Sta/Elev= 30
  4639.5 2070.31  4668.0 2070.21  4683.0 2069.36  4698.1 2067.45  4704.1 2065.30
  4725.1 2060.37  4747.6 2056.16  4797.2 2055.10  4878.3 2050.59  4905.4 2052.15
  4920.4 2051.70  4927.9 2050.67  4964.0 2049.99  4981.0 2048.42  4981.5 2047.92
  4992.1 2048.42  4997.0 2049.60  5003.0 2049.60  5013.6 2051.36  5028.3 2052.24
  5094.4 2052.78  5123.3 2054.66  5211.7 2055.73  5272.3 2057.39  5306.0 2058.22
  5327.3 2060.15  5333.2 2061.70  5400.4 2070.36  5442.8 2077.48  5471.7 2077.82
#Mann=5,-1,0
  4639.5   0.035       0  4981.0   0.035       0  4992.1   0.035       0
  5028.3    0.07       0  5272.3     0.1       0
Bank Sta=4981,4992.1
Exp/Cntr=0.3,0.1

Type RM Length L Ch R = 1,20902,454,454,454
BEGIN DESCRIPTION:
Contrary Creek 42.0
END DESCRIPTION:
XS GIS Cut Line= 3
      1835475.01     13966524.99      1835875.00     13966125.00
      1836075.02     13965974.99
#Sta/Elev= 30
  4438.6 2064.50  4481.0 2062.61  4537.6 2058.62  4646.0 2056.11  4763.9 2053.32
  4820.4 2050.32  4862.9 2049.35  4877.0 2048.34  4919.4 2047.97  4947.7 2044.87
  4970.4 2043.75  4970.9 2043.25  4981.6 2043.75  4990.1 2043.94  5000.7 2047.17
  5007.4 2047.17  5032.4 2049.85  5111.6 2049.81  5140.7 2051.88  5147.0 2054.24
  5160.5 2056.64  5167.8 2061.08  5176.2 2063.01  5182.4 2067.62  5190.7 2070.29
  5197.0 2073.22  5217.8 2079.30  5226.2 2080.49  5253.9 2080.87  5254.3 2080.87
#Mann=5,-1,0
  4438.6   0.035       0  4646.0    0.07       0  4970.4    0.05       0
  4981.6    0.07       0  5253.9     0.1       0
Bank Sta=4970.4,4981.6
Exp/Cntr=0.3,0.1

Type RM Length L Ch R = 1,20448,451,451,451
BEGIN DESCRIPTION:
Contrary Creek 41.0
END DESCRIPTION:
XS GIS Cut Line= 3
      1835824.96     13966575.02      1836175.00     13966375.00
      1836275.01     13966274.99
#Sta/Elev= 30
  4592.2 2055.65  4615.3 2055.35  4643.4 2054.42  4657.7 2054.38  4730.5 2053.68
  4776.5 2052.36  4783.0 2051.87  4811.1 2051.62  4842.0 2050.05  4869.4 2049.51
  4906.8 2047.78  4922.7 2046.20  4944.2 2042.64  4950.0 2042.48  4965.8 2043.41
  4981.7 2042.89  4992.5 2041.33  4998.9 2041.33  5003.9 2040.34  5004.4 2039.84
  5014.6 2039.84  5015.1 2040.34  5023.6 2041.38  5037.8 2044.44  5066.1 2062.07
  5094.4 2074.25  5108.5 2079.20  5122.6 2080.58  5133.2 2082.28  5136.8 2082.28
#Mann=4,-1,0
  4592.2   0.035       0  4657.7    0.07       0  5003.9    0.05       0
  5015.1    0.07       0
Bank Sta=5003.9,5015.1
Exp/Cntr=0.3,0.1

Type RM Length L Ch R = 1,19997,481,481,481
BEGIN DESCRIPTION:
Contrary Creek 40.0
END DESCRIPTION:
XS GIS Cut Line= 3
      1835925.01     13966675.00      1836325.00     13966775.00
      1836474.98     13966625.02
#Sta/Elev= 30
  4587.7 2054.12  4628.9 2053.17  4640.4 2053.26  4701.1 2051.94  4793.8 2046.97
  4853.1 2045.39  4858.3 2045.57  4876.3 2043.98  4894.3 2043.03  4907.2 2042.79
  4917.5 2041.29  4935.6 2040.08  4940.7 2039.43  4969.1 2039.62  4976.8 2038.71
  4989.7 2038.77  4991.8 2038.08  4992.3 2037.58  5002.5 2037.58  5003.0 2038.08
  5028.3 2039.47  5042.4 2041.49  5056.6 2045.44  5084.9 2054.15  5099.0 2057.68
  5141.4 2065.58  5169.7 2072.57  5183.8 2075.56  5198.0 2077.45  5212.1 2078.09
#Mann=4,-1,0
  4587.7   0.035       0  4640.4    0.07       0  4991.8    0.05       0
  5003.0    0.07       0
Bank Sta=4991.8,5003
Exp/Cntr=0.3,0.1

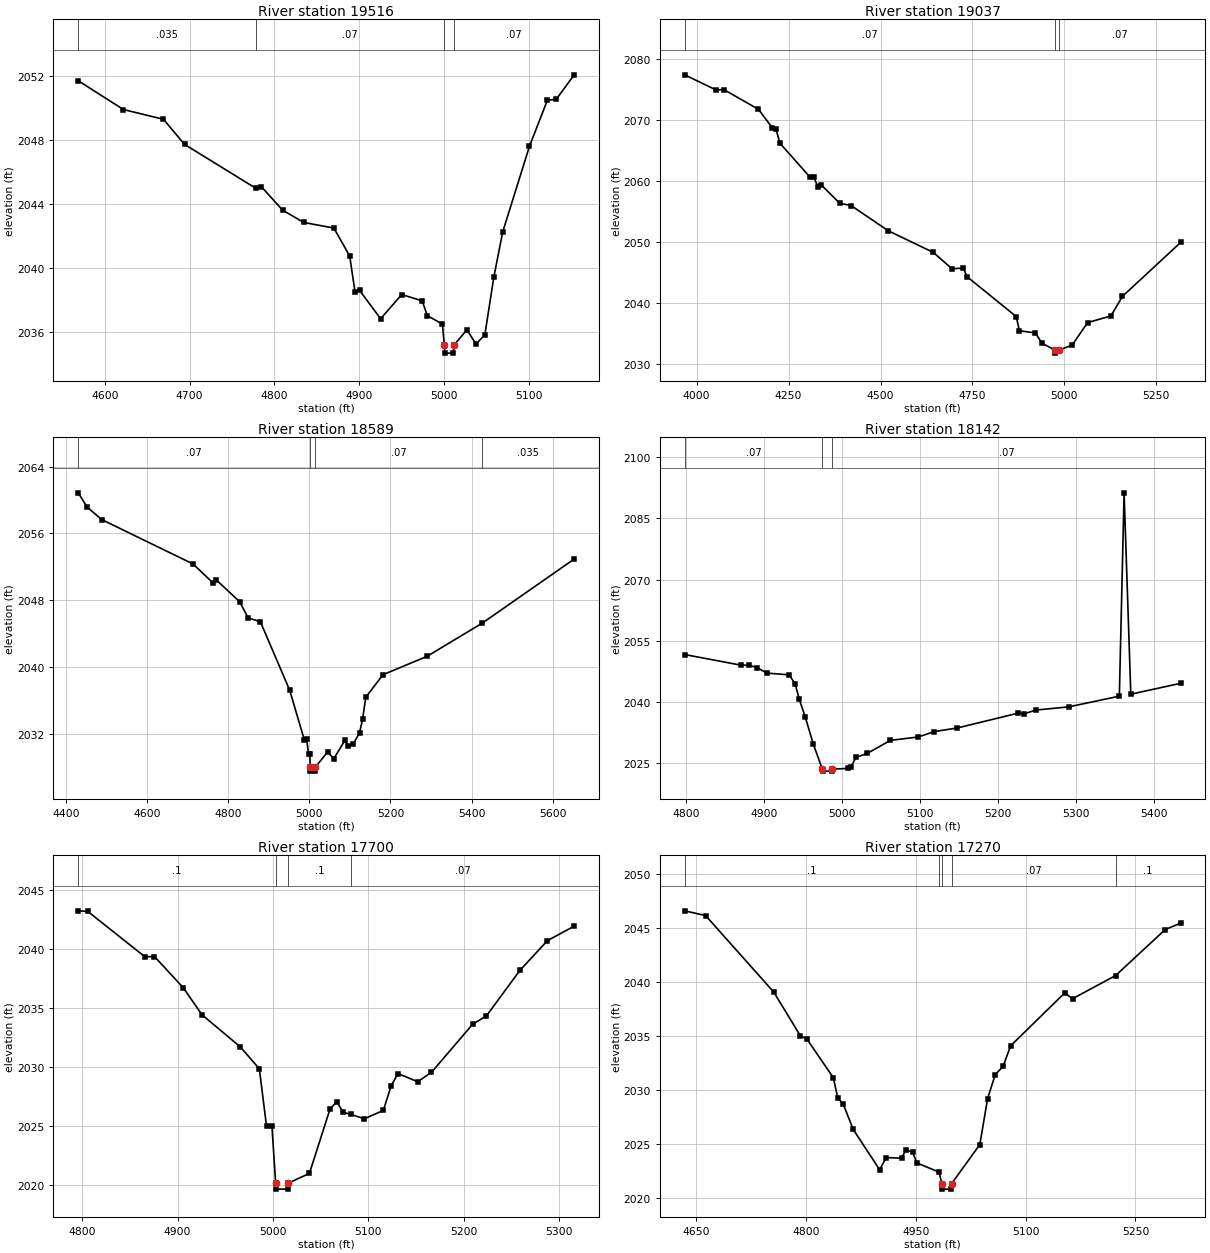
Type RM Length L Ch R = 1,19516,479,479,479
BEGIN DESCRIPTION:
Contrary Creek 39.0
END DESCRIPTION:
XS GIS Cut Line= 3
      1835924.99     13967075.00      1836325.00     13967225.00
      1836474.97     13967175.01
#Sta/Elev= 30
  4568.5 2051.72  4621.9 2049.92  4669.1 2049.31  4694.0 2047.74  4778.0 2045.00
  4784.8 2045.09  4809.7 2043.63  4834.6 2042.86  4870.2 2042.51  4888.9 2040.76
  4895.1 2038.54  4900.5 2038.62  4925.4 2036.84  4950.3 2038.35  4974.4 2037.96
  4980.6 2037.03  4998.3 2036.51  5000.6 2035.19  5001.1 2034.69  5011.4 2034.69
  5011.9 2035.19  5027.3 2036.15  5037.9 2035.26  5048.4 2035.83  5059.0 2039.44
  5069.5 2042.27  5101.1 2047.63  5122.2 2050.50  5132.7 2050.56  5153.8 2052.09
#Mann=4,-1,0
  4568.5   0.035       0  4778.0    0.07       0  5000.6    0.05       0
  5011.9    0.07       0
Bank Sta=5000.6,5011.9
Exp/Cntr=0.3,0.1

Type RM Length L Ch R = 1,19037,448,448,448
BEGIN DESCRIPTION:
Contrary Creek 38.0
END DESCRIPTION:
XS GIS Cut Line= 3
      1835310.57     13967483.12      1836325.00     13967675.00
      1836624.96     13967575.01
#Sta/Elev= 30
  3967.5 2077.39  4053.3 2074.90  4073.8 2074.98  4168.2 2071.74  4206.1 2068.69
  4215.5 2068.59  4226.4 2066.20  4307.9 2060.67  4318.0 2060.73  4330.3 2058.98
  4338.4 2059.40  4389.3 2056.36  4419.8 2056.00  4521.6 2051.85  4643.7 2048.32
  4694.6 2045.64  4725.1 2045.77  4735.3 2044.35  4869.0 2037.83  4877.8 2035.50
  4921.4 2035.14  4938.8 2033.47  4973.9 2032.34  4974.4 2031.84  4985.3 2032.34
  5021.0 2033.14  5063.2 2036.84  5126.4 2037.92  5158.0 2041.14  5316.1 2049.95
#Mann=3,-1,0
  3967.5    0.07       0  4973.9    0.05       0  4985.3    0.07       0
Bank Sta=4973.9,4985.3
Exp/Cntr=0.3,0.1

Type RM Length L Ch R = 1,18589,447,447,447
BEGIN DESCRIPTION:
Contrary Creek 37.0
END DESCRIPTION:
XS GIS Cut Line= 3
      1835798.87     13968390.26      1836275.00     13968075.00
      1836825.03     13967724.98
#Sta/Elev= 30
  4429.9 2060.85  4451.9 2059.14  4488.0 2057.64  4713.1 2052.32  4761.7 2050.08
  4770.8 2050.39  4828.0 2047.80  4849.0 2045.86  4879.1 2045.40  4951.3 2037.20
  4987.4 2031.25  4993.4 2031.38  4997.9 2029.50  5000.9 2029.50  5002.2 2027.99
  5002.7 2027.49  5014.5 2027.49  5015.0 2027.99  5045.0 2029.79  5060.2 2028.97
  5087.3 2031.17  5095.8 2030.48  5108.5 2030.78  5123.7 2032.10  5131.3 2033.73
  5138.9 2036.33  5181.3 2039.04  5290.5 2041.26  5426.0 2045.22  5652.9 2052.91
#Mann=4,-1,0
  4429.9    0.07       0  5002.2    0.05       0  5015.0    0.07       0
  5426.0   0.035       0
Bank Sta=5002.2,5015
Exp/Cntr=0.3,0.1

Type RM Length L Ch R = 1,18142,442,442,442
BEGIN DESCRIPTION:
Contrary Creek 36.0
END DESCRIPTION:
XS GIS Cut Line= 3
      1836425.01     13968624.97      1836475.00     13968425.00
      1836824.97     13968175.02
#Sta/Elev= 30
  4798.3 2051.63  4870.4 2049.03  4880.7 2049.00  4891.0 2048.45  4903.9 2047.08
  4932.3 2046.66  4940.0 2044.44  4945.2 2040.73  4952.9 2036.36  4963.2 2029.76
  4974.8 2023.56  4975.3 2023.06  4987.2 2023.06  4987.7 2023.56  5007.5 2023.72
  5011.8 2024.14  5017.9 2026.42  5032.7 2027.42  5062.2 2030.60  5097.8 2031.42
  5118.7 2032.76  5148.2 2033.64  5225.6 2037.25  5234.2 2037.13  5249.0 2038.03
  5290.8 2038.80  5355.9 2041.43  5362.0 2091.26  5370.6 2041.91  5434.5 2044.58
#Mann=3,-1,0
  4798.3    0.07       0  4974.8    0.05       0  4987.7    0.07       0
Bank Sta=4974.8,4987.7
Exp/Cntr=0.3,0.1

Type RM Length L Ch R = 1,17700,430,430,430
BEGIN DESCRIPTION:
Contrary Creek 35.0
END DESCRIPTION:
XS GIS Cut Line= 3
      1836825.00     13968875.03      1836825.00     13968675.00
      1837025.01     13968424.99
#Sta/Elev= 30
  4795.8 2043.24  4805.8 2043.19  4865.8 2039.35  4875.8 2039.37  4905.8 2036.75
  4925.8 2034.43  4965.8 2031.73  4985.8 2029.87  4993.3 2025.02  4999.0 2025.02
  5002.9 2020.19  5003.4 2019.69  5015.5 2019.69  5016.0 2020.19  5038.3 2021.02
  5059.9 2026.46  5067.1 2027.10  5073.5 2026.20  5081.9 2026.01  5095.9 2025.64
  5115.9 2026.35  5123.9 2028.40  5131.1 2029.47  5151.9 2028.78  5166.3 2029.57
  5209.5 2033.64  5223.9 2034.34  5259.2 2038.21  5288.0 2040.72  5316.0 2041.94
#Mann=4,-1,0
  4795.8     0.1       0  5002.9    0.05       0  5016.0     0.1       0
  5081.9    0.07       0
Bank Sta=5002.9,5016
Exp/Cntr=0.3,0.1

Type RM Length L Ch R = 1,17270,443,443,443
BEGIN DESCRIPTION:
Contrary Creek 34.0
END DESCRIPTION:
XS GIS Cut Line= 3
      1837024.98     13969075.04      1837225.00     13968775.00
      1837324.99     13968475.03
#Sta/Elev= 30
  4634.8 2046.60  4663.4 2046.16  4756.5 2039.06  4792.6 2035.03  4801.6 2034.72
  4837.7 2031.14  4843.7 2029.26  4851.2 2028.70  4864.7 2026.36  4900.8 2022.62
  4909.8 2023.74  4930.8 2023.69  4936.8 2024.47  4945.8 2024.24  4951.8 2023.24
  4981.9 2022.40  4985.8 2021.32  4986.3 2020.82  4998.5 2020.82  4999.0 2021.32
  5037.6 2024.95  5048.1 2029.18  5058.6 2031.43  5069.2 2032.18  5079.7 2034.10
  5153.5 2039.00  5164.1 2038.46  5222.8 2040.60  5290.5 2044.86  5311.6 2045.46
#Mann=5,-1,0
  4634.8     0.1       0  4981.9    0.07       0  4985.8    0.05       0
  4999.0    0.07       0  5222.8     0.1       0
Bank Sta=4985.8,4999
Exp/Cntr=0.3,0.1

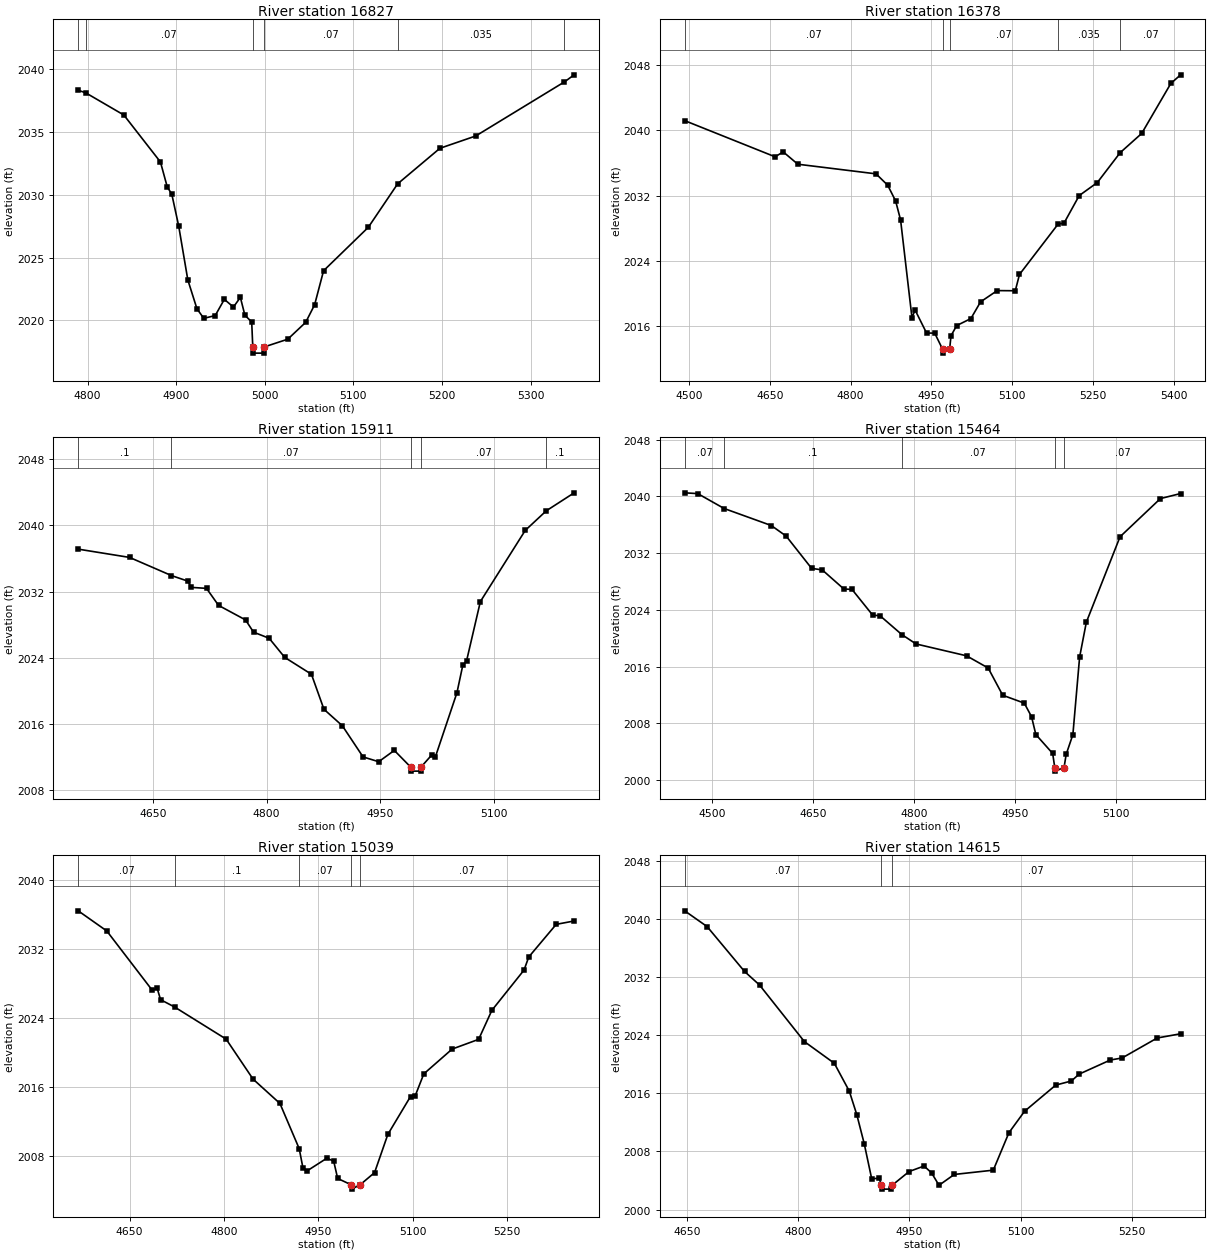
Type RM Length L Ch R = 1,16827,449,449,449
BEGIN DESCRIPTION:
Contrary Creek 33.0
END DESCRIPTION:
XS GIS Cut Line= 3
      1837525.00     13969224.99      1837575.00     13969025.00
      1837625.00     13968675.00
#Sta/Elev= 30
  4789.5 2038.33  4797.9 2038.13  4841.0 2036.36  4882.3 2032.62  4890.0 2030.63
  4895.1 2030.06  4902.9 2027.52  4913.2 2023.23  4923.5 2020.93  4931.2 2020.17
  4944.1 2020.39  4954.4 2021.68  4964.7 2021.07  4972.5 2021.84  4977.6 2020.42
  4985.3 2019.88  4986.5 2017.90  4987.0 2017.40  4999.2 2017.40  4999.7 2017.90
  5026.0 2018.51  5046.2 2019.85  5056.3 2021.25  5066.4 2023.96  5116.9 2027.42
  5150.0 2030.88  5197.7 2033.71  5238.1 2034.69  5338.3 2039.00  5349.2 2039.56
#Mann=6,-1,0
  4789.5   0.035       0  4797.9    0.07       0  4986.5    0.05       0
  4999.7    0.07       0  5150.0   0.035       0  5338.3    0.07       0
Bank Sta=4986.5,4999.7
Exp/Cntr=0.3,0.1

Type RM Length L Ch R = 1,16378,467,467,467
BEGIN DESCRIPTION:
Contrary Creek 32.0
END DESCRIPTION:
XS GIS Cut Line= 3
      1837699.20     13969501.22      1837975.00     13969075.00
      1838075.01     13968674.98
#Sta/Elev= 30
  4492.3 2041.18  4660.0 2036.75  4675.1 2037.35  4702.2 2035.84  4847.3 2034.66
  4868.9 2033.27  4883.6 2031.34  4892.8 2029.02  4913.9 2017.06  4919.8 2017.97
  4941.0 2015.16  4956.1 2015.15  4970.6 2013.20  4971.1 2012.70  4983.8 2013.20
  4986.4 2014.84  4997.0 2016.08  5023.2 2016.93  5041.2 2018.98  5072.1 2020.36
  5105.6 2020.34  5113.4 2022.34  5185.4 2028.54  5195.8 2028.60  5224.2 2032.00
  5257.7 2033.59  5300.1 2037.25  5340.1 2039.61  5394.2 2045.74  5412.3 2046.79
#Mann=5,-1,0
  4492.3    0.07       0  4970.6    0.05       0  4983.8    0.07       0
  5185.4   0.035       0  5300.1    0.07       0
Bank Sta=4970.6,4983.8
Exp/Cntr=0.3,0.1

Type RM Length L Ch R = 1,15911,447,447,447
BEGIN DESCRIPTION:
Contrary Creek 31.0
END DESCRIPTION:
XS GIS Cut Line= 3
      1838314.09     13969458.97      1838425.00     13969025.00
      1838475.01     13968824.97
#Sta/Elev= 30
  4551.6 2037.13  4619.3 2036.13  4674.6 2033.93  4695.8 2033.27  4701.0 2032.50
  4720.8 2032.38  4736.7 2030.32  4772.3 2028.56  4782.8 2027.08  4803.4 2026.34
  4824.0 2024.02  4859.2 2021.98  4875.7 2017.74  4900.0 2015.74  4927.3 2011.97
  4947.9 2011.39  4968.5 2012.76  4990.0 2010.75  4990.5 2010.25  5003.3 2010.25
  5003.8 2010.75  5017.6 2012.18  5022.7 2011.98  5051.1 2019.74  5058.8 2023.06
  5063.9 2023.64  5082.0 2030.78  5141.2 2039.40  5168.9 2041.77  5205.7 2043.95
#Mann=5,-1,0
  4551.6     0.1       0  4674.6    0.07       0  4990.0    0.05       0
  5003.8    0.07       0  5168.9     0.1       0
Bank Sta=4990,5003.8
Exp/Cntr=0.3,0.1

Type RM Length L Ch R = 1,15464,425,425,425
BEGIN DESCRIPTION:
Contrary Creek 30.0
END DESCRIPTION:
XS GIS Cut Line= 3
      1838632.06     13969675.59      1838825.00     13969175.00
      1838825.00     13968974.99
#Sta/Elev= 30
  4458.9 2040.50  4478.3 2040.39  4517.5 2038.29  4587.5 2035.89  4609.6 2034.40
  4647.4 2029.85  4663.2 2029.63  4695.3 2026.94  4707.4 2026.88  4738.2 2023.24
  4748.9 2023.18  4781.3 2020.52  4802.5 2019.19  4877.5 2017.52  4909.6 2015.80
  4931.2 2011.96  4963.2 2010.85  4974.0 2008.94  4980.4 2006.42  5005.4 2003.75
  5008.5 2001.76  5009.0 2001.26  5022.3 2001.76  5025.4 2003.61  5035.4 2006.41
  5045.4 2017.34  5055.4 2022.26  5105.4 2034.30  5165.4 2039.69  5195.4 2040.40
#Mann=5,-1,0
  4458.9    0.07       0  4517.5     0.1       0  4781.3    0.07       0
  5008.5    0.05       0  5022.3    0.07       0
Bank Sta=5008.5,5022.3
Exp/Cntr=0.3,0.1

Type RM Length L Ch R = 1,15039,424,424,424
BEGIN DESCRIPTION:
Contrary Creek 29.0
END DESCRIPTION:
XS GIS Cut Line= 3
      1839025.01     13969774.98      1839175.00     13969375.00
      1839374.98     13969075.03
#Sta/Elev= 30
  4568.4 2036.43  4613.8 2034.09  4685.9 2027.21  4693.9 2027.41  4699.2 2026.11
  4721.4 2025.26  4803.3 2021.53  4846.1 2016.88  4888.8 2014.05  4919.4 2008.80
  4925.3 2006.58  4931.5 2006.20  4963.5 2007.70  4974.2 2007.34  4980.5 2005.34
  5002.1 2004.60  5002.6 2004.10  5016.1 2004.60  5039.1 2006.02  5060.2 2010.46
  5096.2 2014.86  5103.7 2014.95  5117.3 2017.49  5162.3 2020.37  5204.4 2021.50
  5225.4 2024.87  5276.5 2029.55  5284.0 2031.07  5327.6 2034.86  5356.1 2035.25
#Mann=5,-1,0
  4568.4    0.07       0  4721.4     0.1       0  4919.4    0.07       0
  5002.1    0.05       0  5016.1    0.07       0
Bank Sta=5002.1,5016.1
Exp/Cntr=0.3,0.1

Type RM Length L Ch R = 1,14615,425,425,425
BEGIN DESCRIPTION:
Contrary Creek 28.0
END DESCRIPTION:
XS GIS Cut Line= 3
      1839474.99     13969925.04      1839525.00     13969575.00
      1839624.99     13969275.02
#Sta/Elev= 30
  4646.4 2041.12  4676.7 2038.95  4727.2 2032.78  4747.5 2030.91  4808.1 2023.12
  4848.5 2020.14  4868.7 2016.31  4878.8 2013.09  4888.9 2009.07  4899.0 2004.23
  4909.1 2004.33  4912.1 2003.32  4912.6 2002.82  4925.7 2002.82  4926.2 2003.32
  4949.5 2005.24  4969.7 2006.00  4979.8 2005.06  4989.9 2003.35  5010.5 2004.84
  5063.2 2005.43  5084.3 2010.58  5105.4 2013.53  5147.6 2017.14  5168.6 2017.70
  5179.2 2018.65  5221.3 2020.59  5237.2 2020.87  5284.6 2023.62  5316.2 2024.20
#Mann=3,-1,0
  4646.4    0.07       0  4912.1    0.05       0  4926.2    0.07       0
Bank Sta=4912.1,4926.2
Exp/Cntr=0.3,0.1

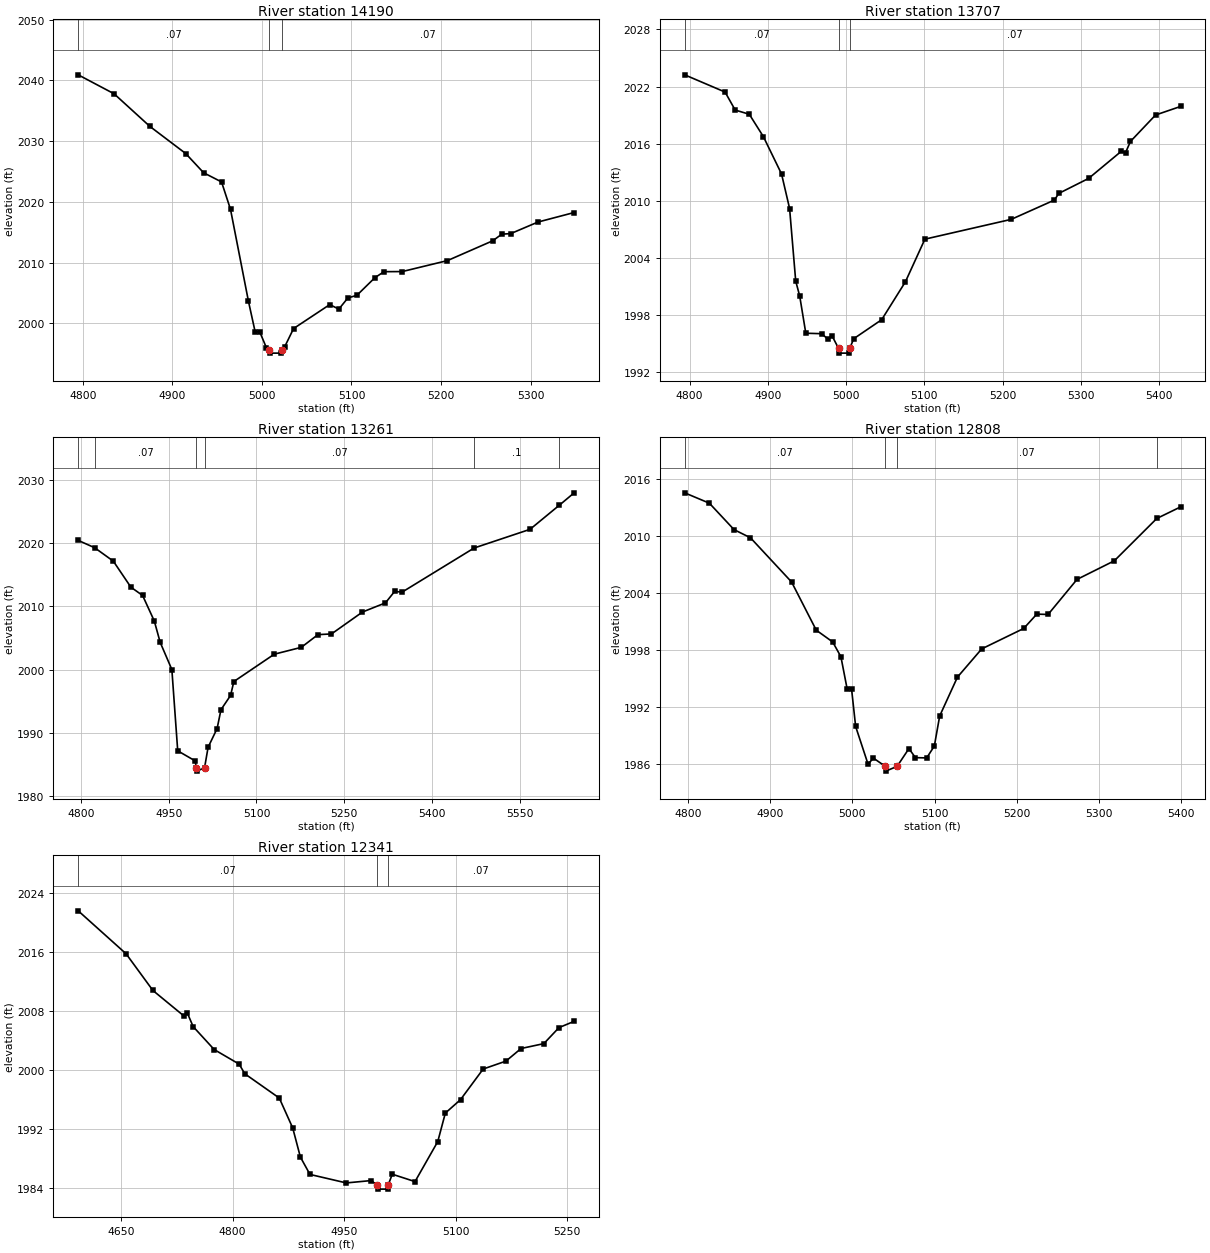
Type RM Length L Ch R = 1,14190,483,483,483
BEGIN DESCRIPTION:
Contrary Creek 27.0
END DESCRIPTION:
XS GIS Cut Line= 3
      1839875.00     13969975.03      1839875.00     13969775.00
      1839825.00     13969424.98
#Sta/Elev= 30
  4795.0 2040.93  4835.0 2037.81  4875.0 2032.43  4915.0 2027.96  4935.0 2024.79
  4955.0 2023.28  4965.0 2018.76  4985.0 2003.64  4992.5 1998.58  4997.6 1998.58
  5005.1 1995.95  5008.2 1995.57  5008.7 1995.07  5021.8 1995.07  5022.3 1995.57
  5025.3 1996.06  5035.4 1999.12  5075.8 2003.07  5085.9 2002.32  5096.0 2004.16
  5106.1 2004.60  5126.3 2007.52  5136.4 2008.49  5156.7 2008.51  5207.2 2010.32
  5257.7 2013.58  5267.8 2014.67  5277.9 2014.77  5308.2 2016.67  5348.6 2018.24
#Mann=3,-1,0
  4795.0    0.07       0  5008.2    0.05       0  5022.3    0.07       0
Bank Sta=5008.2,5022.3
Exp/Cntr=0.3,0.1

Type RM Length L Ch R = 1,13707,446,446,446
BEGIN DESCRIPTION:
Contrary Creek 26.0
END DESCRIPTION:
XS GIS Cut Line= 3
      1840375.01     13969875.05      1840325.00     13969675.00
      1840175.00     13969275.00
#Sta/Elev= 30
  4793.8 2023.23  4845.4 2021.42  4858.3 2019.53  4876.3 2019.09  4894.3 2016.74
  4917.5 2012.82  4927.8 2009.19  4935.6 2001.57  4940.7 2000.00  4948.5 1996.09
  4969.1 1996.04  4976.8 1995.44  4982.0 1995.82  4990.3 1994.50  4990.8 1994.00
  5004.0 1994.00  5004.5 1994.50  5009.8 1995.52  5045.4 1997.51  5075.7 2001.49
  5100.6 2005.97  5210.9 2008.05  5266.1 2010.08  5271.5 2010.77  5309.7 2012.35
  5351.6 2015.21  5356.9 2015.06  5363.1 2016.23  5395.2 2019.01  5427.2 2019.91
#Mann=3,-1,0
  4793.8    0.07       0  4990.3    0.05       0  5004.5    0.07       0
Bank Sta=4990.3,5004.5
Exp/Cntr=0.3,0.1

Type RM Length L Ch R = 1,13261,453,453,453
BEGIN DESCRIPTION:
Contrary Creek 25.0
END DESCRIPTION:
XS GIS Cut Line= 3
      1840725.00     13969724.95      1840725.00     13969525.00
      1840456.70     13968935.87
#Sta/Elev= 30
  4795.5 2020.43  4823.5 2019.28  4855.5 2017.15  4885.5 2013.04  4905.5 2011.73
  4925.5 2007.69  4935.5 2004.33  4955.5 2000.02  4965.5 1987.18  4995.5 1985.58
  4997.1 1984.47  4997.6 1983.97  5011.3 1984.47  5017.4 1987.74  5032.8 1990.70
  5039.4 1993.68  5055.8 1995.93  5061.4 1998.13  5130.5 2002.45  5176.6 2003.53
  5205.1 2005.54  5228.2 2005.65  5281.1 2009.11  5320.4 2010.56  5336.1 2012.37
  5348.9 2012.26  5471.9 2019.23  5567.4 2022.18  5617.7 2026.01  5642.8 2027.95
#Mann=6,-1,0
  4795.5   0.035       0  4823.5    0.07       0  4997.1    0.05       0
  5011.3    0.07       0  5471.9     0.1       0  5617.7   0.035       0
Bank Sta=4997.1,5011.3
Exp/Cntr=0.3,0.1

Type RM Length L Ch R = 1,12808,467,467,467
BEGIN DESCRIPTION:
Contrary Creek 24.0
END DESCRIPTION:
XS GIS Cut Line= 3
      1841125.00     13969574.99      1841125.00     13969375.00
      1840925.00     13969025.00
#Sta/Elev= 30
  4796.2 2014.54  4826.2 2013.45  4856.2 2010.67  4876.2 2009.81  4926.2 2005.16
  4956.2 2000.09  4976.2 1998.85  4986.2 1997.29  4993.7 1993.94  4999.1 1993.94
  5004.1 1989.96  5019.2 1985.99  5025.7 1986.63  5040.2 1985.76  5040.7 1985.26
  5054.5 1985.76  5068.9 1987.63  5076.8 1986.68  5090.5 1986.65  5099.8 1987.90
  5106.3 1991.06  5127.9 1995.15  5157.4 1998.12  5208.5 2000.27  5224.4 2001.78
  5238.1 2001.74  5273.3 2005.43  5318.7 2007.39  5370.3 2011.84  5399.3 2013.06
#Mann=4,-1,0
  4796.2    0.07       0  5040.2    0.05       0  5054.5    0.07       0
  5370.3     0.1       0
Bank Sta=5040.2,5054.5
Exp/Cntr=0.3,0.1

Type RM Length L Ch R = 1,12341,173,173,173
BEGIN DESCRIPTION:
Contrary Creek 23.0
END DESCRIPTION:
XS GIS Cut Line= 3
      1841524.99     13969474.96      1841425.00     13969075.00
      1841175.02     13969025.00
#Sta/Elev= 30
  4592.2 2021.59  4656.6 2015.77  4692.7 2010.80  4733.9 2007.39  4739.0 2007.75
  4746.8 2005.91  4775.1 2002.80  4808.6 2000.83  4816.4 1999.51  4862.7 1996.23
  4880.8 1992.17  4891.1 1988.23  4904.0 1985.88  4952.9 1984.73  4986.4 1985.05
  4994.7 1984.39  4995.2 1983.89  5008.5 1983.89  5009.0 1984.39  5014.7 1985.91
  5045.3 1984.91  5075.9 1990.33  5086.1 1994.19  5106.5 1996.01  5137.0 2000.16
  5167.6 2001.23  5188.0 2002.94  5218.6 2003.60  5239.0 2005.77  5259.4 2006.62
#Mann=3,-1,0
  4592.2    0.07       0  4994.7    0.05       0  5009.0    0.07       0
Bank Sta=4994.7,5009
Exp/Cntr=0.3,0.1