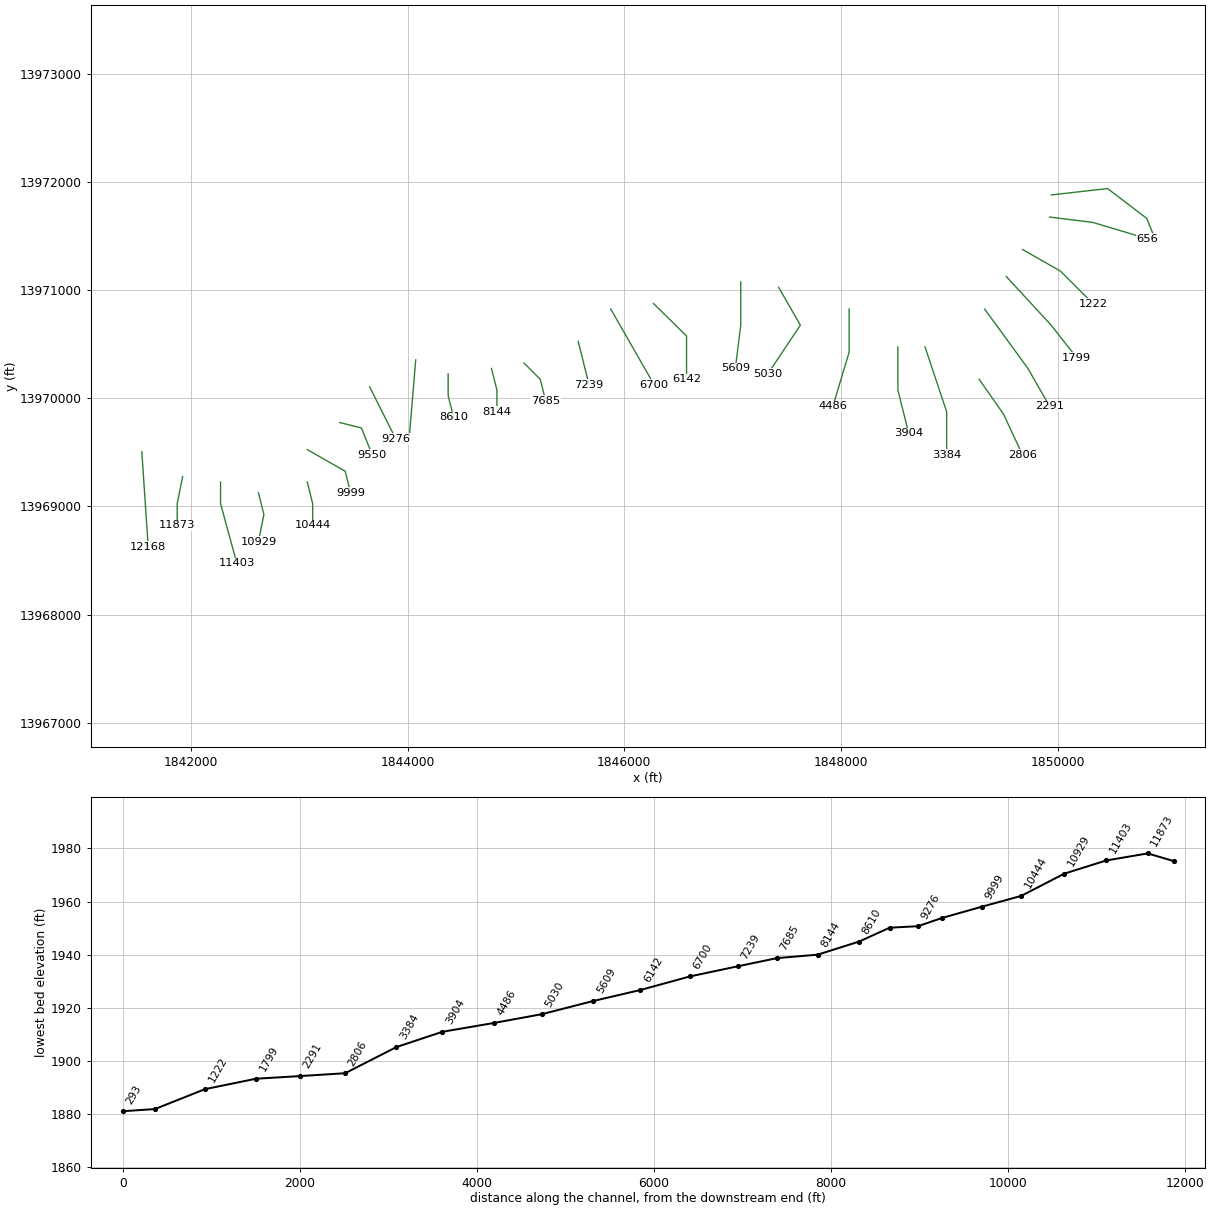
HEC-RAS study Contrary Creek.prj: Contrary Creek Base Level Engineering

--- Contrary Creek.g01 (geometry) --- (continued)

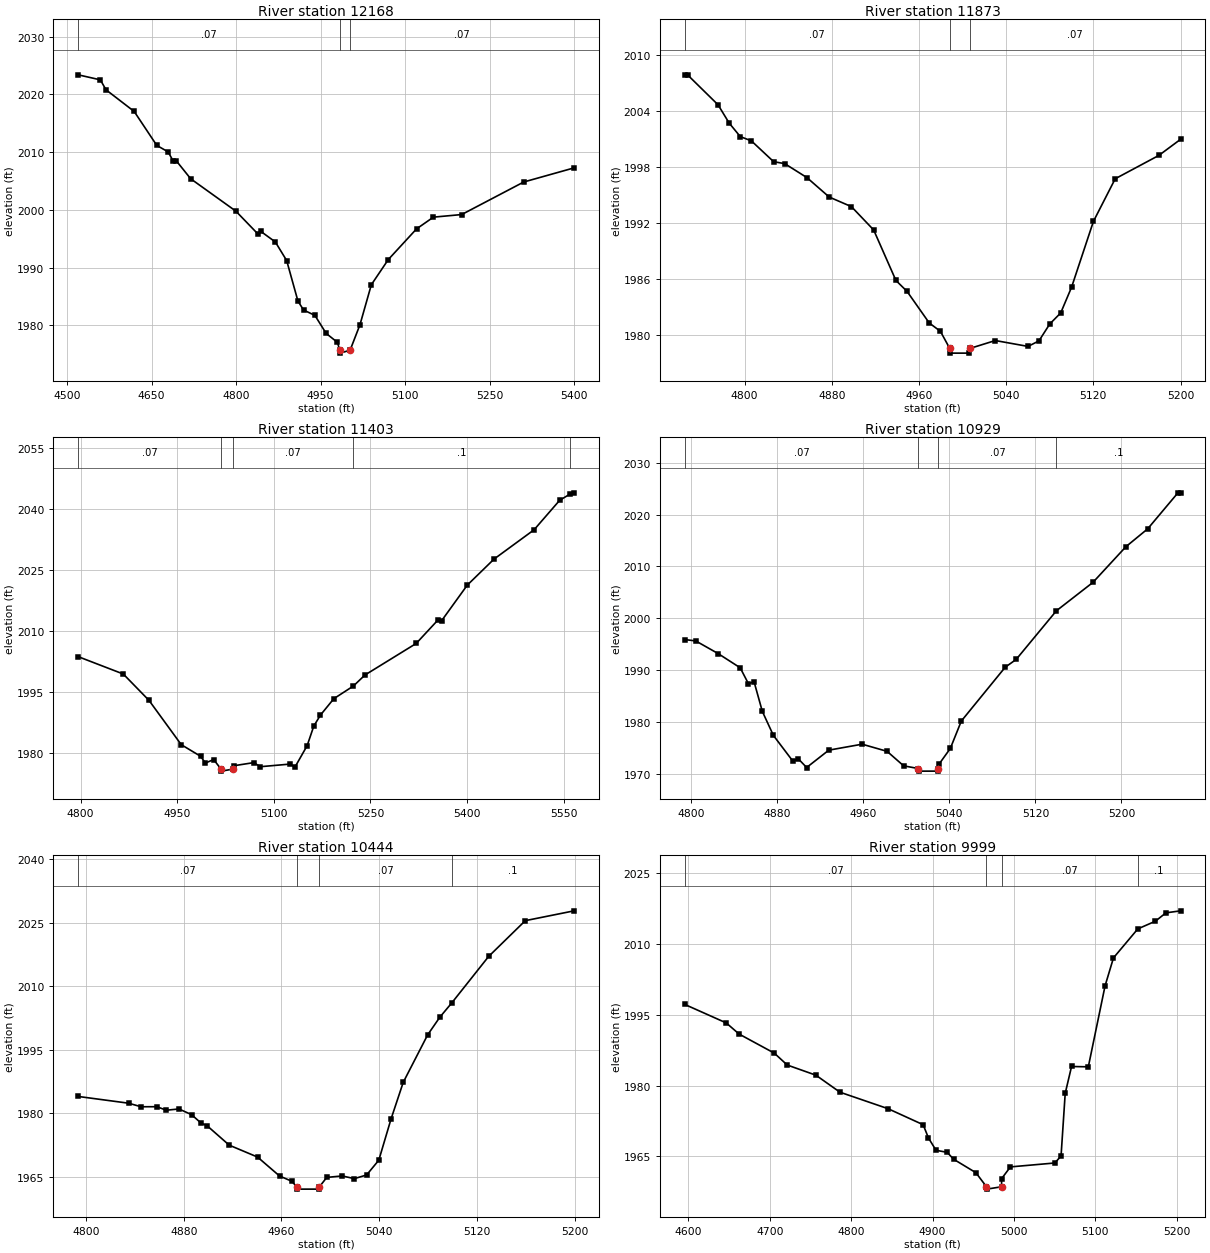
Type RM Length L Ch R = 1,12168,295,295,295
BEGIN DESCRIPTION:
Mapping XS ba1f2b17
END DESCRIPTION:
XS GIS Cut Line= 2
      1841548.38     13969504.22      1841607.41     13968625.70
#Sta/Elev= 30
  4519.7 2023.40  4559.0 2022.53  4569.0 2020.81  4619.1 2017.05  4659.2 2011.17
  4679.3 2010.05  4688.7 2008.40  4693.7 2008.52  4719.4 2005.39  4799.6 1999.78
  4838.4 1995.86  4843.4 1996.31  4869.7 1994.44  4889.8 1991.22  4909.8 1984.20
  4919.8 1982.65  4939.9 1981.72  4959.9 1978.60  4980.0 1977.04  4984.0 1975.68
  4984.5 1975.18  5002.4 1975.68  5020.0 1980.12  5040.1 1987.03  5070.2 1991.39
  5120.3 1996.70  5150.3 1998.74  5200.5 1999.19  5310.7 2004.83  5400.2 2007.28
#Mann=3,-1,0
  4519.7    0.07       0  4984.0    0.05       0  5002.4    0.07       0
Bank Sta=4984,5002.4
Exp/Cntr=0.3,0.1

Type RM Length L Ch R = 1,11873,470,470,470
BEGIN DESCRIPTION:
Contrary Creek 22.0
END DESCRIPTION:
XS GIS Cut Line= 3
      1841925.01     13969275.04      1841875.00     13969025.00
      1841875.00     13968824.99
#Sta/Elev= 30
  4745.1 2007.92  4747.7 2007.92  4775.7 2004.71  4785.9 2002.75  4796.1 2001.30
  4806.3 2000.84  4826.7 1998.61  4836.9 1998.40  4857.3 1996.90  4877.7 1994.82
  4898.1 1993.79  4918.5 1991.29  4938.9 1985.88  4949.1 1984.71  4969.5 1981.32
  4979.7 1980.43  4988.3 1978.59  4988.8 1978.09  5006.2 1978.09  5006.7 1978.59
  5030.1 1979.44  5060.1 1978.81  5070.1 1979.40  5080.1 1981.22  5090.1 1982.40
  5100.1 1985.17  5120.1 1992.21  5140.1 1996.78  5180.1 1999.28  5200.1 2001.01
#Mann=3,-1,0
  4745.1    0.07       0  4988.3    0.05       0  5006.7    0.07       0
Bank Sta=4988.3,5006.7
Exp/Cntr=0.3,0.1

Type RM Length L Ch R = 1,11403,474,474,474
BEGIN DESCRIPTION:
Contrary Creek 21.0
END DESCRIPTION:
XS GIS Cut Line= 3
      1842275.00     13969224.98      1842275.00     13969025.00
      1842425.01     13968474.97
#Sta/Elev= 30
  4796.2 2003.59  4866.2 1999.32  4906.2 1992.82  4956.2 1981.94  4986.2 1979.09
  4993.7 1977.42  5006.5 1978.28  5018.0 1975.93  5018.5 1975.43  5036.5 1975.93
  5037.6 1976.75  5068.7 1977.52  5079.1 1976.52  5125.7 1977.17  5132.7 1976.40
  5151.7 1981.70  5162.0 1986.51  5172.4 1989.23  5193.1 1993.25  5223.5 1996.37
  5241.5 1999.08  5321.0 2006.84  5355.5 2012.73  5360.7 2012.48  5400.4 2021.20
  5441.9 2027.60  5504.1 2034.81  5543.8 2042.06  5559.9 2043.59  5566.3 2043.90
#Mann=5,-1,0
  4796.2    0.07       0  5018.0    0.05       0  5036.5    0.07       0
  5223.5     0.1       0  5559.9    0.07       0
Bank Sta=5018,5036.5
Exp/Cntr=0.3,0.1

Type RM Length L Ch R = 1,10929,485,485,485
BEGIN DESCRIPTION:
Contrary Creek 20.0
END DESCRIPTION:
XS GIS Cut Line= 3
      1842624.99     13969125.03      1842675.00     13968925.00
      1842625.01     13968675.04
#Sta/Elev= 30
  4793.9 1995.87  4804.2 1995.60  4824.9 1993.17  4845.5 1990.42  4853.2 1987.33
  4858.4 1987.73  4866.1 1981.99  4876.4 1977.35  4894.4 1972.41  4899.6 1972.82
  4907.3 1971.16  4927.9 1974.51  4958.9 1975.66  4982.1 1974.28  4997.5 1971.48
  5011.2 1970.96  5011.7 1970.46  5029.2 1970.46  5029.7 1970.96  5030.7 1971.90
  5040.9 1974.85  5051.1 1980.13  5091.9 1990.52  5102.1 1992.03  5139.5 2001.42
  5173.5 2006.91  5204.1 2013.79  5224.4 2017.25  5252.5 2024.20  5255.0 2024.20
#Mann=4,-1,0
  4793.9    0.07       0  5011.2    0.05       0  5029.7    0.07       0
  5139.5     0.1       0
Bank Sta=5011.2,5029.7
Exp/Cntr=0.3,0.1

Type RM Length L Ch R = 1,10444,445,445,445
BEGIN DESCRIPTION:
Contrary Creek 19.0
END DESCRIPTION:
XS GIS Cut Line= 3
      1843075.00     13969225.00      1843125.00     13969025.00
      1843125.00     13968824.96
#Sta/Elev= 30
  4793.5 1983.99  4834.7 1982.40  4845.0 1981.56  4857.9 1981.57  4865.7 1980.74
  4876.0 1981.04  4886.3 1979.70  4894.0 1977.74  4899.2 1977.04  4917.2 1972.49
  4940.4 1969.68  4958.4 1965.21  4968.7 1963.94  4972.4 1962.61  4972.9 1962.11
  4990.4 1962.11  4990.9 1962.61  4997.1 1964.88  5009.7 1965.22  5019.7 1964.59
  5029.7 1965.45  5039.7 1968.94  5049.7 1978.65  5059.7 1987.32  5079.7 1998.53
  5089.7 2002.71  5099.5 2006.09  5129.7 2017.06  5159.7 2025.50  5199.7 2027.82
#Mann=4,-1,0
  4793.5    0.07       0  4972.4    0.05       0  4990.9    0.07       0
  5099.5     0.1       0
Bank Sta=4972.4,4990.9
Exp/Cntr=0.3,0.1

Type RM Length L Ch R = 1,9999,449,449,449
BEGIN DESCRIPTION:
Contrary Creek 18.0
END DESCRIPTION:
XS GIS Cut Line= 3
      1843075.00     13969525.00      1843425.00     13969325.00
      1843475.01     13969124.97
#Sta/Elev= 30
  4595.5 1997.19  4646.6 1993.26  4662.4 1990.90  4705.6 1986.86  4721.5 1984.34
  4756.7 1982.19  4786.3 1978.58  4845.3 1975.09  4888.5 1971.69  4895.0 1968.88
  4904.3 1966.27  4918.0 1965.84  4925.9 1964.38  4953.3 1961.52  4966.3 1958.54
  4966.8 1958.04  4984.8 1958.54  4984.9 1960.27  4995.7 1962.75  5050.2 1963.58
  5057.9 1965.05  5063.0 1978.33  5070.8 1984.03  5091.4 1983.96  5112.0 2001.13
  5122.3 2007.05  5152.2 2013.19  5173.8 2014.82  5186.7 2016.59  5204.8 2017.02
#Mann=4,-1,0
  4595.5    0.07       0  4966.3    0.05       0  4984.8    0.07       0
  5152.2     0.1       0
Bank Sta=4966.3,4984.8
Exp/Cntr=0.3,0.1

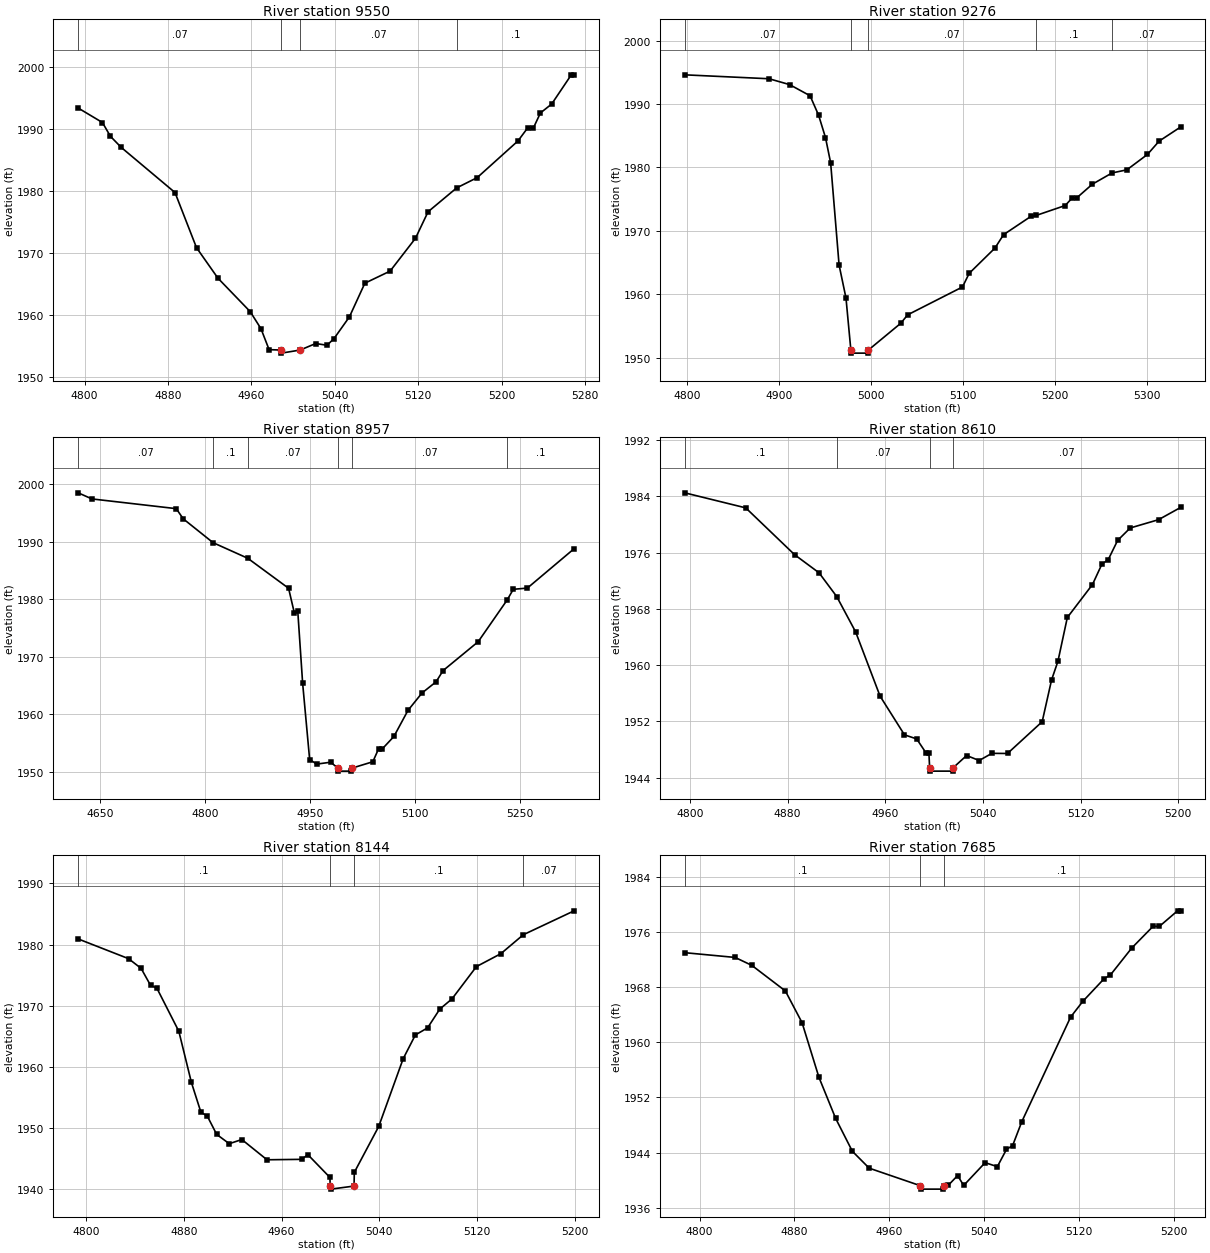
Type RM Length L Ch R = 1,9550,274,274,274
BEGIN DESCRIPTION:
Contrary Creek 17.0
END DESCRIPTION:
XS GIS Cut Line= 3
      1843375.01     13969775.00      1843575.00     13969725.00
      1843675.00     13969475.00
#Sta/Elev= 30
  4793.9 1993.35  4817.1 1991.02  4824.8 1988.79  4835.1 1987.01  4886.7 1979.72
  4907.3 1970.83  4927.9 1965.90  4958.8 1960.51  4969.1 1957.76  4976.9 1954.38
  4988.2 1954.32  4988.7 1953.82  5006.7 1954.32  5021.6 1955.37  5032.4 1955.09
  5039.1 1956.16  5053.9 1959.67  5068.7 1965.10  5092.9 1967.05  5117.2 1972.34
  5129.3 1976.62  5156.7 1980.47  5176.4 1982.13  5215.5 1988.05  5224.9 1990.18
  5230.3 1990.15  5237.0 1992.56  5247.8 1994.00  5266.6 1998.71  5269.3 1998.71
#Mann=4,-1,0
  4793.9    0.07       0  4988.2    0.05       0  5006.7    0.07       0
  5156.7     0.1       0
Bank Sta=4988.2,5006.7
Exp/Cntr=0.3,0.1

Type RM Length L Ch R = 1,9276,319,319,319
BEGIN DESCRIPTION:
Mapping XS 5c5da1da
END DESCRIPTION:
XS GIS Cut Line= 2
      1843650.51     13970105.24      1843892.27     13969622.72
#Sta/Elev= 30
  4797.4 1994.62  4889.2 1994.00  4911.5 1993.08  4933.8 1991.32  4943.1 1988.25
  4950.6 1984.72  4956.2 1980.75  4965.4 1964.61  4972.9 1959.41  4978.2 1951.21
  4978.7 1950.71  4996.9 1950.71  4997.4 1951.21  5032.6 1955.43  5040.0 1956.75
  5099.7 1961.15  5107.0 1963.30  5135.0 1967.28  5144.4 1969.40  5174.1 1972.28
  5179.8 1972.43  5211.5 1974.00  5218.8 1975.15  5224.4 1975.25  5241.1 1977.37
  5262.5 1979.14  5278.6 1979.63  5301.0 1982.06  5313.7 1984.16  5337.1 1986.39
#Mann=5,-1,0
  4797.4    0.07       0  4978.2    0.05       0  4997.4    0.07       0
  5179.8     0.1       0  5262.5    0.07       0
Bank Sta=4978.2,4997.4
Exp/Cntr=0.3,0.1

Type RM Length L Ch R = 1,8957,347,347,347
BEGIN DESCRIPTION:
Mapping XS 393d4d59
END DESCRIPTION:
XS GIS Cut Line= 2
      1844075.81     13970354.58      1844017.16     13969648.41
#Sta/Elev= 30
  4619.1 1998.49  4638.7 1997.43  4759.2 1995.74  4769.2 1993.97  4811.8 1989.83
  4861.4 1987.12  4919.7 1981.91  4927.8 1977.69  4932.8 1977.99  4939.8 1965.39
  4949.8 1952.16  4959.9 1951.36  4979.9 1951.69  4990.3 1950.64  4990.8 1950.14
  5009.2 1950.14  5009.7 1950.64  5040.1 1951.77  5048.4 1954.04  5053.4 1953.98
  5070.2 1956.16  5090.3 1960.69  5110.4 1963.72  5130.4 1965.65  5140.5 1967.61
  5190.6 1972.62  5232.0 1979.87  5240.8 1981.73  5260.9 1981.94  5327.7 1988.78
#Mann=6,-1,0
  4619.1    0.07       0  4811.8     0.1       0  4861.4    0.07       0
  4990.3    0.05       0  5009.7    0.07       0  5232.0     0.1       0
Bank Sta=4990.3,5009.7
Exp/Cntr=0.3,0.1

Type RM Length L Ch R = 1,8610,466,466,466
BEGIN DESCRIPTION:
Contrary Creek 16.0
END DESCRIPTION:
XS GIS Cut Line= 3
      1844375.00     13970225.02      1844375.00     13970025.00
      1844425.01     13969824.97
#Sta/Elev= 30
  4795.8 1984.49  4845.8 1982.35  4885.8 1975.69  4905.8 1973.12  4920.3 1969.74
  4935.8 1964.71  4955.8 1955.58  4975.8 1950.07  4985.8 1949.49  4993.3 1947.54
  4995.8 1947.54  4996.4 1945.41  4996.9 1944.91  5015.3 1944.91  5015.8 1945.41
  5026.7 1947.13  5037.0 1946.42  5047.4 1947.44  5060.2 1947.42  5088.6 1951.94
  5096.3 1957.89  5101.5 1960.53  5109.2 1966.76  5129.8 1971.45  5137.5 1974.34
  5142.7 1974.99  5150.4 1977.72  5160.7 1979.49  5183.9 1980.67  5202.0 1982.41
#Mann=4,-1,0
  4795.8     0.1       0  4920.3    0.07       0  4996.4    0.05       0
  5015.8    0.07       0
Bank Sta=4996.4,5015.8
Exp/Cntr=0.3,0.1

Type RM Length L Ch R = 1,8144,459,459,459
BEGIN DESCRIPTION:
Contrary Creek 15.0
END DESCRIPTION:
XS GIS Cut Line= 3
      1844775.01     13970274.98      1844825.00     13970075.00
      1844825.00     13969875.03
#Sta/Elev= 30
  4793.5 1980.91  4834.7 1977.69  4845.0 1976.10  4852.7 1973.34  4857.9 1972.87
  4875.9 1965.81  4886.2 1957.44  4894.0 1952.56  4899.1 1951.98  4906.9 1948.95
  4917.2 1947.43  4927.5 1948.11  4948.1 1944.80  4976.4 1944.87  4981.6 1945.63
  4999.6 1941.92  4999.9 1940.50  5000.4 1940.00  5019.4 1940.50  5019.6 1942.74
  5039.6 1950.25  5059.6 1961.32  5069.6 1965.21  5079.6 1966.37  5089.6 1969.44
  5099.6 1971.11  5119.6 1976.39  5139.6 1978.50  5158.0 1981.60  5199.6 1985.51
#Mann=4,-1,0
  4793.5     0.1       0  4999.9    0.05       0  5019.4     0.1       0
  5158.0    0.07       0
Bank Sta=4999.9,5019.4
Exp/Cntr=0.3,0.1

Type RM Length L Ch R = 1,7685,446,446,446
BEGIN DESCRIPTION:
Contrary Creek 14.0
END DESCRIPTION:
XS GIS Cut Line= 3
      1845074.98     13970325.02      1845225.00     13970175.00
      1845275.00     13969975.01
#Sta/Elev= 30
  4787.5 1973.00  4830.0 1972.31  4844.1 1971.16  4872.4 1967.45  4886.5 1962.84
  4900.7 1954.93  4914.8 1948.97  4928.9 1944.20  4943.1 1941.75  4986.2 1939.21
  4986.7 1938.71  5005.6 1938.71  5006.1 1939.21  5010.0 1939.30  5017.7 1940.68
  5022.8 1939.24  5040.9 1942.55  5051.2 1941.97  5058.9 1944.47  5064.1 1945.03
  5071.8 1948.48  5113.0 1963.66  5123.3 1965.94  5141.4 1969.25  5146.5 1969.75
  5164.6 1973.68  5182.6 1976.83  5187.8 1976.80  5203.2 1979.07  5205.8 1979.07
#Mann=3,-1,0
  4787.5     0.1       0  4986.2    0.05       0  5006.1     0.1       0
Bank Sta=4986.2,5006.1
Exp/Cntr=0.3,0.1

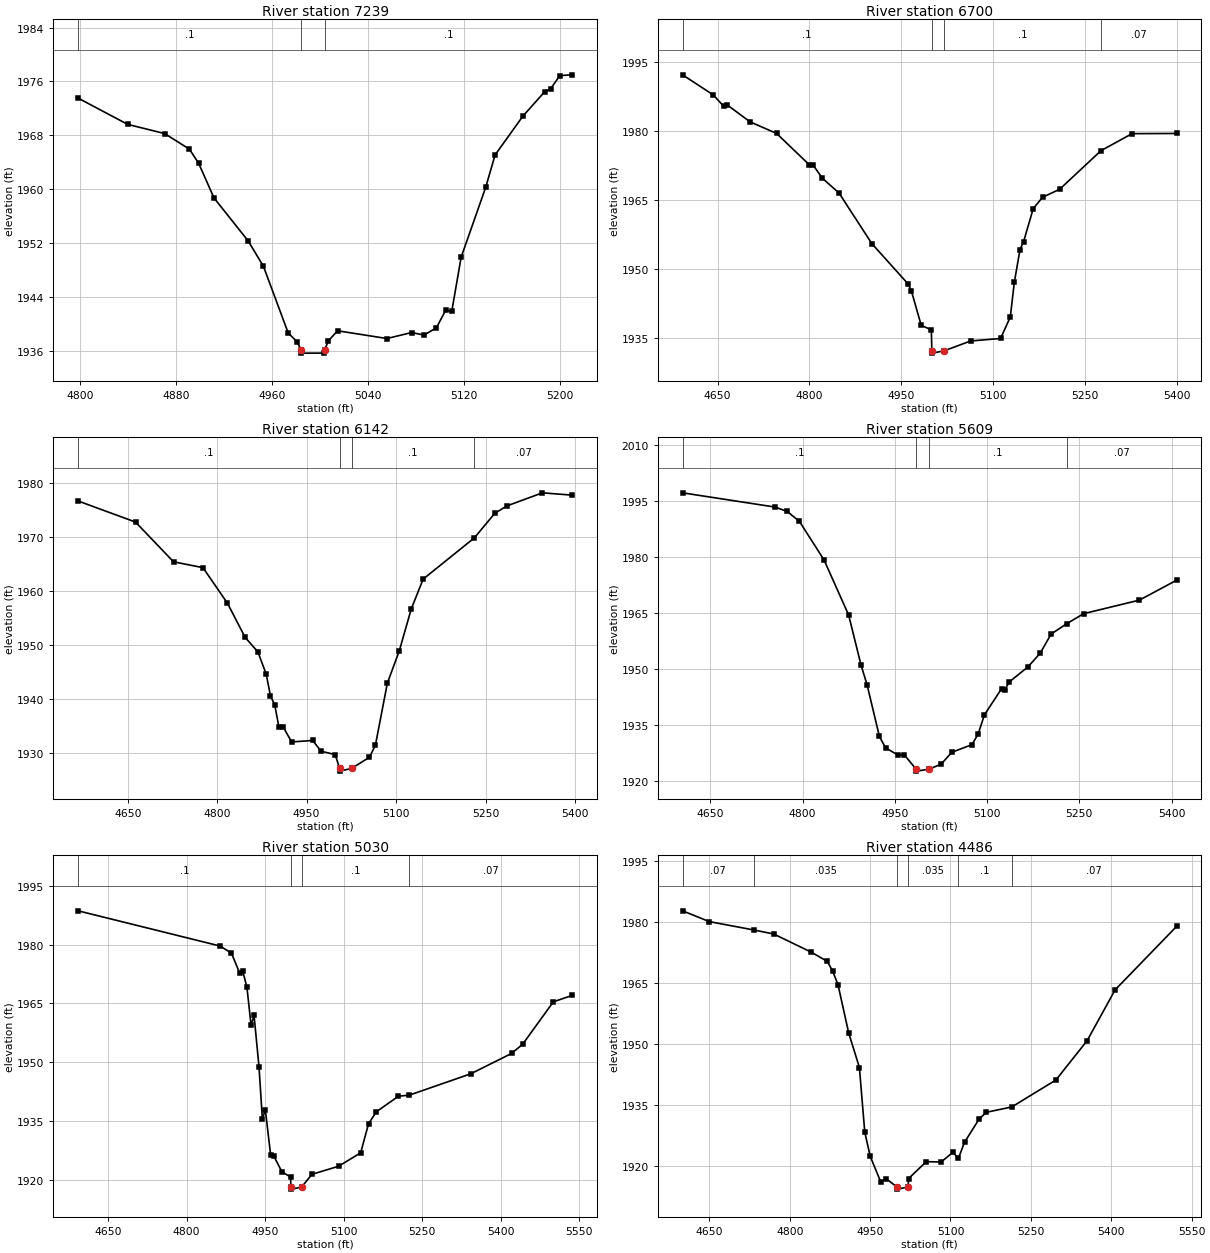
Type RM Length L Ch R = 1,7239,539,539,539
BEGIN DESCRIPTION:
Contrary Creek 13.0
END DESCRIPTION:
XS GIS Cut Line= 3
      1845574.99     13970525.03      1845625.00     13970325.00
      1845674.99     13970125.04
#Sta/Elev= 30
  4798.1 1973.51  4839.4 1969.61  4870.3 1968.24  4890.9 1965.93  4898.6 1963.85
  4911.5 1958.67  4939.9 1952.31  4952.7 1948.53  4973.4 1938.61  4981.1 1937.24
  4984.0 1936.11  4984.5 1935.61  5003.4 1935.61  5003.9 1936.11  5006.9 1937.43
  5014.6 1938.93  5055.8 1937.78  5076.4 1938.67  5086.8 1938.29  5097.1 1939.38
  5104.8 1941.99  5109.9 1941.82  5117.7 1949.85  5138.3 1960.30  5146.0 1965.05
  5169.2 1970.82  5187.3 1974.43  5192.4 1974.90  5200.1 1976.86  5210.4 1976.97
#Mann=3,-1,0
  4798.1     0.1       0  4984.0    0.05       0  5003.9     0.1       0
Bank Sta=4984,5003.9
Exp/Cntr=0.3,0.1

Type RM Length L Ch R = 1,6700,558,558,558
BEGIN DESCRIPTION:
Contrary Creek 12.0
END DESCRIPTION:
XS GIS Cut Line= 3
      1845874.99     13970825.02      1846075.00     13970475.00
      1846275.02     13970124.96
#Sta/Elev= 30
  4592.9 1992.23  4643.3 1987.84  4659.9 1985.42  4665.6 1985.71  4703.1 1982.02
  4746.3 1979.51  4799.5 1972.73  4805.3 1972.76  4821.1 1969.78  4848.5 1966.53
  4901.7 1955.60  4960.8 1946.85  4966.5 1945.25  4982.4 1937.82  4998.9 1936.89
  4999.7 1932.31  5000.2 1931.81  5019.8 1932.31  5063.0 1934.45  5111.9 1934.99
  5127.8 1939.68  5134.3 1947.20  5143.6 1954.29  5149.4 1956.00  5165.2 1963.20
  5180.3 1965.63  5208.4 1967.40  5275.6 1975.75  5326.4 1979.46  5399.2 1979.50
#Mann=4,-1,0
  4592.9     0.1       0  4999.7    0.05       0  5019.8     0.1       0
  5275.6    0.07       0
Bank Sta=4999.7,5019.8
Exp/Cntr=0.3,0.1

Type RM Length L Ch R = 1,6142,533,533,533
BEGIN DESCRIPTION:
Contrary Creek 11.0
END DESCRIPTION:
XS GIS Cut Line= 3
      1846269.57     13970875.73      1846575.00     13970575.00
      1846575.00     13970175.03
#Sta/Elev= 30
  4566.8 1976.67  4663.1 1972.77  4726.8 1965.42  4776.2 1964.34  4817.3 1957.75
  4846.9 1951.44  4868.2 1948.78  4882.3 1944.62  4889.4 1940.60  4896.5 1938.98
  4903.5 1934.87  4910.6 1934.90  4924.8 1932.11  4960.1 1932.38  4974.2 1930.40
  4997.9 1929.76  5005.4 1927.21  5005.9 1926.71  5025.5 1927.21  5055.4 1929.28
  5065.4 1931.53  5085.4 1942.98  5105.4 1948.96  5125.4 1956.67  5145.4 1962.22
  5231.4 1969.86  5265.4 1974.37  5285.4 1975.74  5345.4 1978.18  5395.4 1977.75
#Mann=4,-1,0
  4566.8     0.1       0  5005.4    0.05       0  5025.5     0.1       0
  5231.4    0.07       0
Bank Sta=5005.4,5025.5
Exp/Cntr=0.3,0.1

Type RM Length L Ch R = 1,5609,579,579,579
BEGIN DESCRIPTION:
Contrary Creek 10.0
END DESCRIPTION:
XS GIS Cut Line= 3
      1847075.00     13971075.04      1847075.00     13970675.00
      1847024.99     13970274.96
#Sta/Elev= 30
  4605.0 1997.23  4755.0 1993.42  4775.0 1992.25  4795.0 1989.57  4835.0 1979.23
  4875.0 1964.45  4895.0 1951.12  4905.0 1945.71  4925.0 1931.88  4935.0 1928.83
  4955.0 1926.91  4965.0 1927.04  4984.8 1923.08  4985.3 1922.58  5005.3 1923.08
  5025.2 1924.44  5042.8 1927.63  5075.6 1929.70  5085.7 1932.63  5095.7 1937.66
  5123.5 1944.67  5128.5 1944.37  5136.1 1946.50  5166.3 1950.52  5186.4 1954.21
  5204.1 1959.34  5229.3 1962.10  5257.0 1964.82  5347.7 1968.45  5408.2 1973.80
#Mann=4,-1,0
  4605.0     0.1       0  4984.8    0.05       0  5005.3     0.1       0
  5229.3    0.07       0
Bank Sta=4984.8,5005.3
Exp/Cntr=0.3,0.1

Type RM Length L Ch R = 1,5030,544,544,544
BEGIN DESCRIPTION:
Contrary Creek 9.0
END DESCRIPTION:
XS GIS Cut Line= 3
      1847425.02     13971024.97      1847625.00     13970675.00
      1847325.00     13970225.01
#Sta/Elev= 30
  4592.7 1988.60  4864.0 1979.62  4885.6 1977.81  4901.5 1972.67  4907.2 1973.22
  4915.2 1969.09  4923.1 1959.41  4928.8 1961.92  4938.2 1948.90  4944.7 1935.54
  4950.4 1937.86  4960.5 1926.29  4966.3 1926.14  4982.1 1922.01  4998.8 1920.72
  4999.0 1918.13  4999.5 1917.63  5019.5 1918.13  5039.3 1921.40  5090.4 1923.47
  5132.5 1926.90  5147.5 1934.30  5162.5 1937.36  5204.6 1941.32  5225.5 1941.60
  5342.8 1947.04  5420.9 1952.24  5442.0 1954.59  5500.6 1965.40  5536.6 1967.03
#Mann=4,-1,0
  4592.7     0.1       0  4999.0    0.05       0  5019.5     0.1       0
  5225.5    0.07       0
Bank Sta=4999,5019.5
Exp/Cntr=0.3,0.1

Type RM Length L Ch R = 1,4486,582,582,582
BEGIN DESCRIPTION:
Contrary Creek 8.0
END DESCRIPTION:
XS GIS Cut Line= 3
      1848075.00     13970825.02      1848075.00     13970425.00
      1847925.01     13969925.04
#Sta/Elev= 30
  4600.0 1982.68  4650.0 1980.03  4733.2 1977.97  4770.0 1976.99  4840.0 1972.54
  4870.0 1970.27  4880.0 1967.91  4890.0 1964.57  4910.0 1952.70  4930.0 1944.19
  4940.0 1928.35  4950.0 1922.44  4970.0 1916.03  4980.0 1916.88  5000.2 1914.81
  5000.7 1914.31  5020.8 1914.81  5021.8 1916.92  5054.8 1921.05  5082.7 1920.99
  5104.4 1923.34  5114.8 1921.88  5126.2 1925.84  5154.0 1931.64  5167.1 1933.19
  5214.4 1934.50  5296.7 1941.12  5355.0 1950.79  5407.2 1963.27  5522.0 1978.87
#Mann=6,-1,0
  4600.0    0.07       0  4733.2   0.035       0  5000.2   0.035       0
  5020.8   0.035       0  5114.8     0.1       0  5214.4    0.07       0
Bank Sta=5000.2,5020.8
Exp/Cntr=0.3,0.1

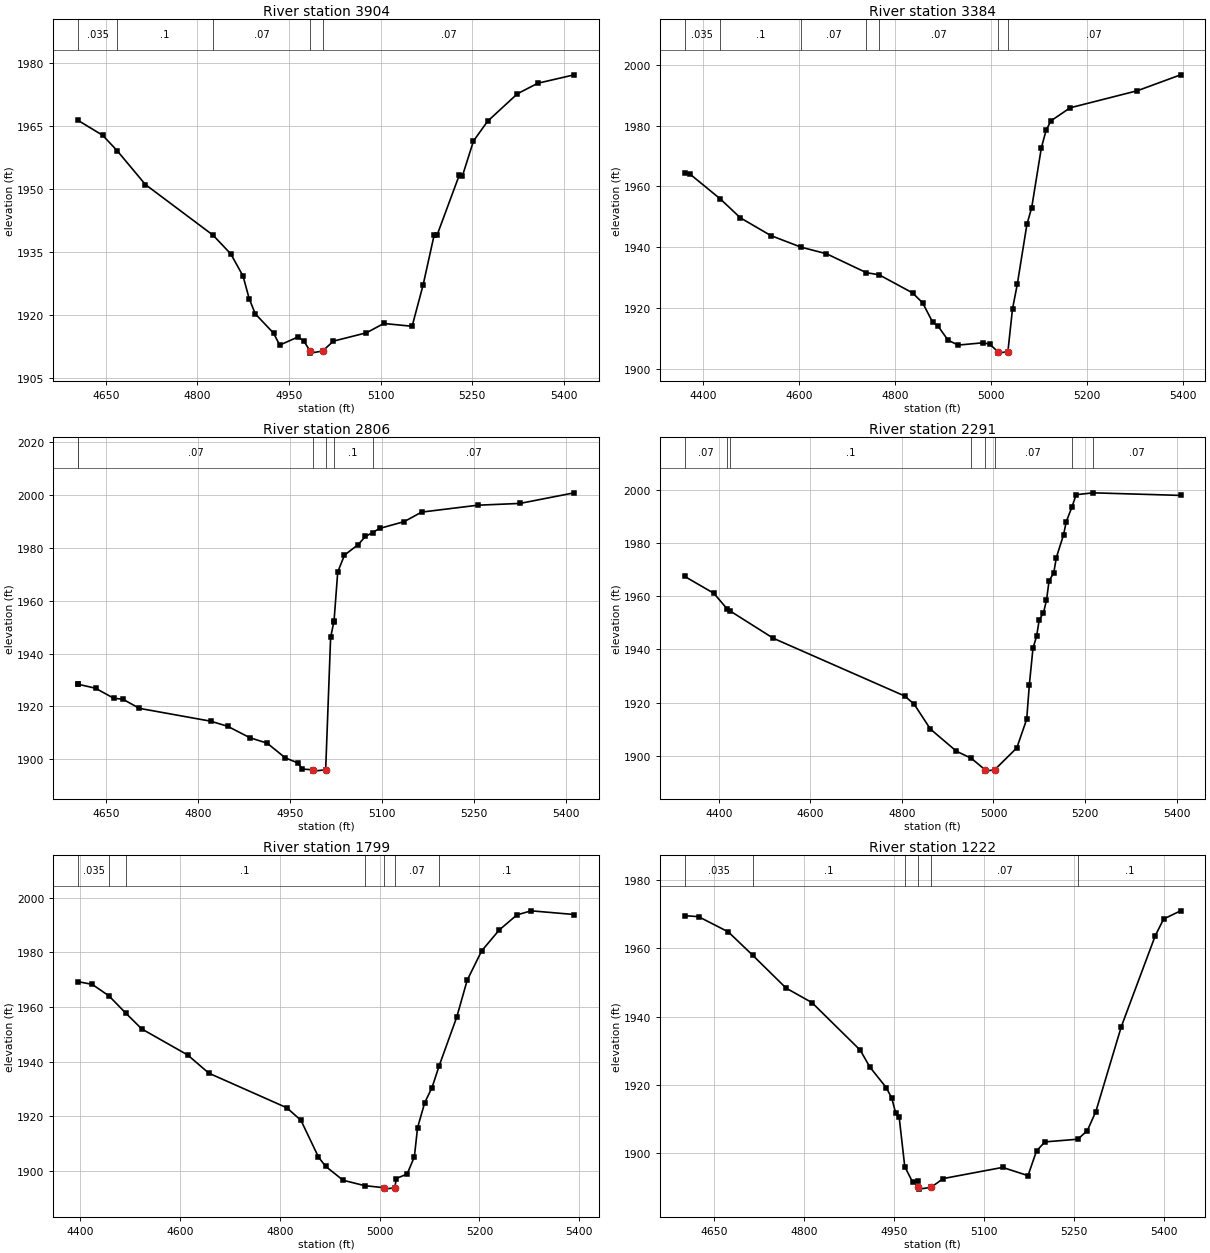
Type RM Length L Ch R = 1,3904,520,520,520
BEGIN DESCRIPTION:
Contrary Creek 7.0
END DESCRIPTION:
XS GIS Cut Line= 3
      1848525.00     13970474.98      1848525.00     13970075.00
      1848625.00     13969674.99
#Sta/Elev= 30
  4604.8 1966.26  4644.8 1962.75  4668.5 1959.10  4714.8 1951.05  4825.9 1938.98
  4854.8 1934.54  4874.8 1929.29  4884.8 1923.95  4894.8 1920.32  4924.8 1915.73
  4934.8 1912.90  4964.8 1914.83  4974.8 1913.80  4984.4 1911.49  4984.9 1910.99
  5005.1 1911.49  5022.8 1913.84  5076.9 1915.82  5105.3 1918.03  5151.7 1917.37
  5169.7 1927.18  5187.7 1938.99  5192.9 1939.15  5229.0 1953.30  5234.1 1953.09
  5252.2 1961.39  5275.4 1966.09  5324.3 1972.63  5357.8 1975.12  5417.1 1977.11
#Mann=5,-1,0
  4604.8   0.035       0  4668.5     0.1       0  4825.9    0.07       0
  4984.4    0.05       0  5005.1    0.07       0
Bank Sta=4984.4,5005.1
Exp/Cntr=0.3,0.1

Type RM Length L Ch R = 1,3384,578,578,578
BEGIN DESCRIPTION:
Contrary Creek 6.0
END DESCRIPTION:
XS GIS Cut Line= 3
      1848775.00     13970475.00      1848975.00     13969875.00
      1848975.00     13969474.95
#Sta/Elev= 30
  4362.5 1964.26  4373.0 1964.11  4436.4 1955.92  4478.4 1949.68  4541.7 1943.86
  4604.7 1940.04  4657.6 1937.88  4740.9 1931.65  4767.2 1930.97  4836.8 1925.03
  4857.9 1921.75  4879.0 1915.31  4889.5 1914.21  4910.6 1909.51  4931.7 1907.87
  4984.4 1908.64  4997.5 1908.14  5014.6 1905.73  5015.1 1905.23  5035.4 1905.73
  5045.0 1919.75  5055.0 1927.88  5075.0 1947.52  5085.0 1953.04  5105.0 1972.64
  5115.0 1978.46  5125.0 1981.54  5165.0 1985.82  5305.0 1991.43  5395.0 1996.65
#Mann=7,-1,0
  4362.5   0.035       0  4436.4     0.1       0  4604.7    0.07       0
  4740.9     0.1       0  4767.2    0.07       0  5014.6    0.05       0
  5035.4    0.07       0
Bank Sta=5014.6,5035.4
Exp/Cntr=0.3,0.1

Type RM Length L Ch R = 1,2806,515,515,515
BEGIN DESCRIPTION:
Contrary Creek 5.0
END DESCRIPTION:
XS GIS Cut Line= 3
      1849275.03     13970174.96      1849500.33     13969851.80
      1849675.02     13969474.97
#Sta/Elev= 30
  4604.0 1928.33  4604.2 1928.33  4632.3 1926.83  4662.0 1923.03  4676.8 1922.68
  4703.8 1919.21  4819.9 1914.35  4847.8 1912.42  4884.3 1908.06  4912.4 1906.00
  4942.1 1900.40  4963.0 1898.48  4969.7 1896.19  4986.9 1895.91  4987.4 1895.41
  5007.8 1895.91  5015.9 1946.09  5021.1 1951.98  5021.5 1952.43  5027.5 1970.91
  5038.5 1977.29  5060.5 1981.23  5072.8 1984.36  5084.5 1985.87  5095.7 1987.40
  5136.0 1990.00  5164.4 1993.60  5256.1 1996.22  5324.8 1996.89  5413.3 2000.91
#Mann=6,-1,0
  4604.0   0.035       0  4604.2    0.07       0  4986.9    0.05       0
  5007.8    0.07       0  5021.1     0.1       0  5084.5    0.07       0
Bank Sta=4986.9,5007.8
Exp/Cntr=0.3,0.1

Type RM Length L Ch R = 1,2291,492,492,492
BEGIN DESCRIPTION:
Contrary Creek 4.0
END DESCRIPTION:
XS GIS Cut Line= 3
      1849325.02     13970824.97      1849725.00     13970275.00
      1849925.02     13969924.96
#Sta/Elev= 30
  4325.5 1967.40  4389.2 1961.05  4418.8 1955.09  4424.5 1954.45  4519.1 1944.18
  4805.8 1922.53  4826.6 1919.48  4862.2 1910.10  4919.0 1901.79  4951.7 1899.12
  4981.6 1894.82  4982.1 1894.32  5002.5 1894.82  5050.9 1903.04  5072.5 1913.80
  5078.2 1926.56  5086.2 1940.41  5094.1 1944.96  5099.8 1950.99  5109.2 1953.80
  5115.7 1958.39  5121.4 1965.78  5131.5 1968.66  5137.3 1974.49  5153.1 1983.09
  5158.9 1987.95  5171.2 1993.36  5180.5 1998.06  5217.3 1998.77  5408.7 1997.80
#Mann=8,-1,0
  4325.5    0.07       0  4418.8   0.035       0  4424.5     0.1       0
  4951.7    0.07       0  4981.6    0.05       0  5002.5    0.07       0
  5171.2     0.1       0  5217.3    0.07       0
Bank Sta=4981.6,5002.5
Exp/Cntr=0.3,0.1

Type RM Length L Ch R = 1,1799,577,577,577
BEGIN DESCRIPTION:
Contrary Creek 3.0
END DESCRIPTION:
XS GIS Cut Line= 3
      1849525.02     13971124.98      1849938.31     13970676.02
      1850175.03     13970374.97
#Sta/Elev= 30
  4396.5 1969.30  4424.5 1968.33  4458.0 1964.12  4491.5 1957.84  4523.8 1952.00
  4615.7 1942.47  4658.2 1935.79  4814.2 1923.14  4842.5 1918.55  4877.7 1905.08
  4891.8 1901.71  4927.0 1896.59  4970.0 1894.62  5009.6 1893.84  5010.1 1893.34
  5030.5 1893.84  5033.5 1897.21  5055.3 1898.90  5069.7 1905.17  5076.1 1915.83
  5090.5 1925.04  5105.0 1930.50  5119.1 1938.37  5154.7 1956.42  5175.5 1969.86
  5204.4 1980.57  5239.7 1988.25  5275.2 1993.78  5303.8 1995.26  5389.7 1993.91
#Mann=7,-1,0
  4396.5   0.035       0  4458.0    0.07       0  4491.5     0.1       0
  4970.0    0.07       0  5009.6    0.05       0  5030.5    0.07       0
  5119.1     0.1       0
Bank Sta=5009.6,5030.5
Exp/Cntr=0.3,0.1

Type RM Length L Ch R = 1,1222,566,566,566
BEGIN DESCRIPTION:
Contrary Creek 2.0
END DESCRIPTION:
XS GIS Cut Line= 3
      1849674.97     13971375.01      1850025.00     13971175.00
      1850325.00     13970875.00
#Sta/Elev= 30
  4601.1 1969.60  4624.2 1969.31  4673.8 1964.85  4714.3 1958.04  4770.3 1948.36
  4813.5 1944.10  4894.1 1930.14  4909.9 1925.24  4937.3 1919.20  4946.7 1916.05
  4953.1 1911.71  4958.9 1910.54  4968.3 1895.99  4981.2 1891.55  4990.6 1891.82
  4990.9 1889.91  4991.4 1889.41  5011.9 1889.91  5032.5 1892.51  5131.5 1895.78
  5173.9 1893.37  5188.1 1900.62  5202.2 1903.26  5257.1 1904.05  5272.9 1906.59
  5287.1 1912.17  5329.5 1937.04  5386.1 1963.68  5400.2 1968.63  5428.5 1971.02
#Mann=6,-1,0
  4601.1   0.035       0  4714.3     0.1       0  4968.3    0.07       0
  4990.9    0.05       0  5011.9    0.07       0  5257.1     0.1       0
Bank Sta=4990.9,5011.9
Exp/Cntr=0.3,0.1

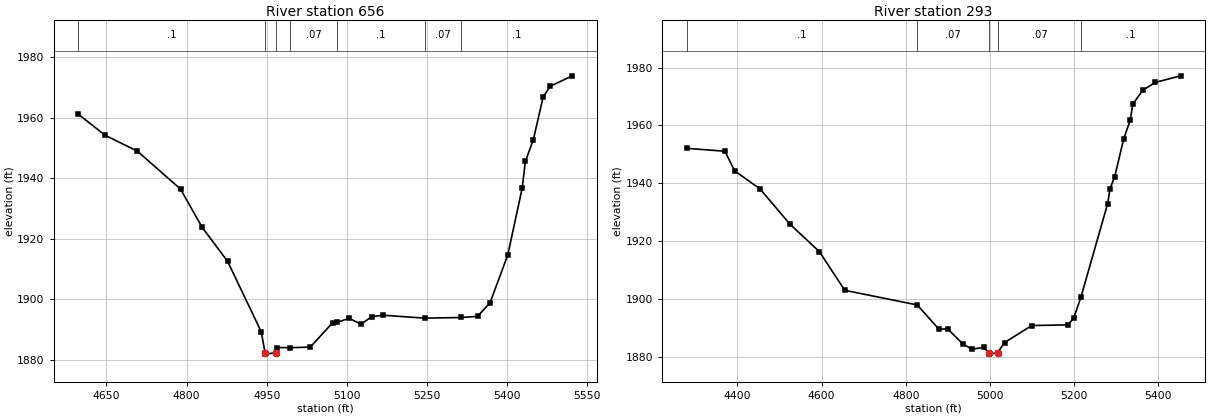
Type RM Length L Ch R = 1,656,363,363,363
BEGIN DESCRIPTION:
Contrary Creek 1.0
END DESCRIPTION:
XS GIS Cut Line= 3
      1849925.01     13971675.00      1850325.00     13971625.00
      1850824.98     13971475.01
#Sta/Elev= 30
  4597.2 1961.25  4647.6 1954.27  4708.0 1949.01  4788.7 1936.48  4829.0 1923.89
  4876.9 1912.57  4939.8 1889.33  4947.0 1882.42  4947.5 1881.92  4968.0 1882.42
  4970.1 1884.10  4993.8 1884.06  5031.6 1884.23  5073.4 1892.27  5081.1 1892.42
  5104.7 1893.75  5126.5 1891.80  5146.5 1894.28  5167.3 1894.79  5245.8 1893.82
  5314.7 1894.03  5344.8 1894.40  5368.3 1898.91  5401.4 1914.70  5428.4 1936.73
  5434.4 1945.66  5449.2 1952.74  5467.5 1966.83  5480.6 1970.46  5522.3 1973.93
#Mann=7,-1,0
  4597.2     0.1       0  4947.0    0.05       0  4968.0     0.1       0
  4993.8    0.07       0  5081.1     0.1       0  5245.8    0.07       0
  5314.7     0.1       0
Bank Sta=4947,4968
Exp/Cntr=0.3,0.1

Type RM Length L Ch R = 1,293,0,0,0
BEGIN DESCRIPTION:
Contrary Creek 0.0
END DESCRIPTION:
XS GIS Cut Line= 4
      1849941.88     13971879.43      1850459.61     13971938.44
      1850820.85     13971662.82      1850895.27     13971479.52
#Sta/Elev= 30
  4279.7 1952.12  4370.7 1951.11  4393.6 1944.35  4453.9 1938.12  4524.4 1926.04
  4594.9 1916.48  4655.2 1903.13  4827.5 1898.07  4878.7 1889.72  4899.5 1889.82
  4934.9 1884.71  4957.6 1882.81  4984.8 1883.46  4997.0 1881.61  4997.5 1881.11
  5018.1 1881.61  5034.6 1885.10  5099.1 1890.97  5184.9 1891.21  5198.8 1893.49
  5216.4 1900.95  5279.6 1933.08  5285.2 1938.23  5296.0 1942.19  5317.6 1955.37
  5333.2 1961.88  5339.2 1967.34  5362.7 1972.15  5393.1 1974.88  5453.0 1977.13
#Mann=5,-1,0
  4279.7     0.1       0  4827.5    0.07       0  4997.0    0.05       0
  5018.1    0.07       0  5216.4     0.1       0
Bank Sta=4997,5018.1
Exp/Cntr=0.3,0.1

Chan Stop Cuts=-1