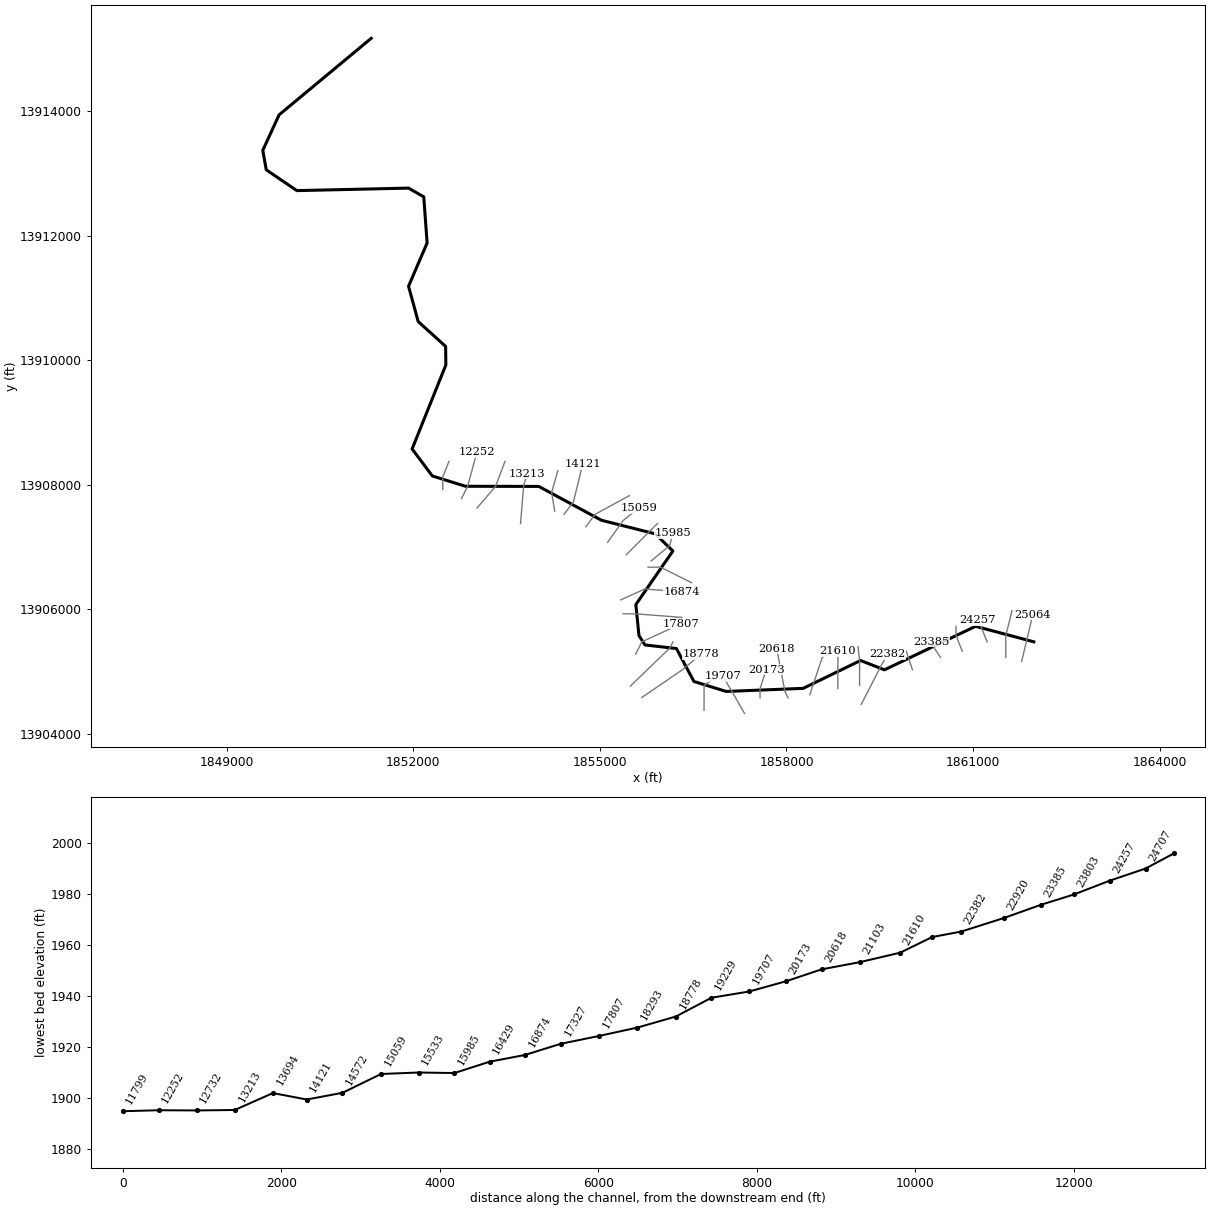
--- Cypress Creek 2.prj (project) ---

Proj Title=Cypress Creek 2 Base Level Engineering
Current Plan=p01
Default Exp/Contr=0.3,0.1
English Units
Geom File=g01
Flow File=f01
Plan File=p01
BEGIN DESCRIPTION:
Cypress Creek 2
END DESCRIPTION:

--- Cypress Creek 2.p01 (plan) ---

Plan Title=Multiple Run
Short Identifier=Multiple
Geom File=g01
Flow File=f01
Subcritical Flow
K Sum by GR= 0
Std Step Tol= 0.01
Critical Tol= 0.01
Num of Std Step Trials= 20
Max Error Tol= 0.3
Flow Tol Ratio= 0.001
Split Flow NTrial= 30
Split Flow Tol= 0.02
Split Flow Ratio= 0.02
Log Output Level= 0
Friction Slope Method= 1
Unsteady Friction Slope Method= 2
Unsteady Bridges Friction Slope Method= 1
Parabolic Critical Depth
Global Vel Dist=  1 , 1 , 1
Global Log Level= 0
CheckData=True
Encroach Param= -1, 0, 0, 0
BEGIN DESCRIPTION:
Multiple Run
END DESCRIPTION:

--- Cypress Creek 2.f01 (steady flow) ---

Flow Title=Multiple
Number of Profiles=7
Profile Names=10-year,25-year,50-year,1pct_min,100-year,1pct_plu,500-year
River Rch & RM= Cypress Creek 2,Reach-1,25064
    1740    3057    4348    2985    5956   11883   11052
River Rch & RM= Cypress Creek 2,Reach-1,22382
    3544    6413    9296    6487   12942   25823   24827
River Rch & RM= Cypress Creek 2,Reach-1,17807
    5617   10377   15255   10782   21514   42926   42352
River Rch & RM= Cypress Creek 2,Reach-1,14121
    5672   10493   15435   10912   21771   43440   42898
River Rch & RM= Cypress Creek 2,Reach-1,9585
    5752   10617   15592   11002   21952   43800   43092
River Rch & RM= Cypress Creek 2,Reach-1,4404
    6007   11090   16287   11488   22922   45736   44949
River Rch & RM= Cypress Creek 2,Reach-1,606
    6366   11777   17320   12233   24407   48698   47982
Boundary for River Rch & Prof#=Cypress Creek 2,Reach-1,1
Up Type=0
Dn Type=3
Dn Slope=0.005
Boundary for River Rch & Prof#=Cypress Creek 2,Reach-1,2
Up Type=0
Dn Type=3
Dn Slope=0.005
Boundary for River Rch & Prof#=Cypress Creek 2,Reach-1,3
Up Type=0
Dn Type=3
Dn Slope=0.005
Boundary for River Rch & Prof#=Cypress Creek 2,Reach-1,4
Up Type=0
Dn Type=3
Dn Slope=0.005
Boundary for River Rch & Prof#=Cypress Creek 2,Reach-1,5
Up Type=0
Dn Type=3
Dn Slope=0.005
Boundary for River Rch & Prof#=Cypress Creek 2,Reach-1,6
Up Type=0
Dn Type=3
Dn Slope=0.005
Boundary for River Rch & Prof#=Cypress Creek 2,Reach-1,7
Up Type=0
Dn Type=3
Dn Slope=0.005

--- Cypress Creek 2.g01 (geometry) ---

Geom Title=Existing Conditions

River Reach=Cypress Creek 2,Reach-1
Reach XY= 30
      1861975.00     13905475.00      1861038.97     13905724.45
      1859575.00     13905025.00      1859190.40     13905174.91
      1858269.07     13904727.25      1857030.93     13904677.24
      1856511.70     13904838.40      1856231.21     13905367.20
      1855725.00     13905425.00      1855628.75     13905576.55
      1855578.75     13906073.45      1856174.30     13906935.71
      1855888.33     13907211.35      1855026.46     13907428.54
      1854019.07     13907972.76      1852840.27     13907975.38
      1852308.22     13908140.69      1851982.53     13908574.99
      1852525.00     13909925.00      1852521.26     13910223.45
      1852080.54     13910622.58      1851925.09     13911190.39
      1852223.83     13911885.48      1852169.66     13912627.74
      1851925.10     13912767.67      1850130.53     13912727.38
      1849638.37     13913061.68      1849582.56     13913375.00
      1849844.62     13913945.47      1851325.00     13915175.00

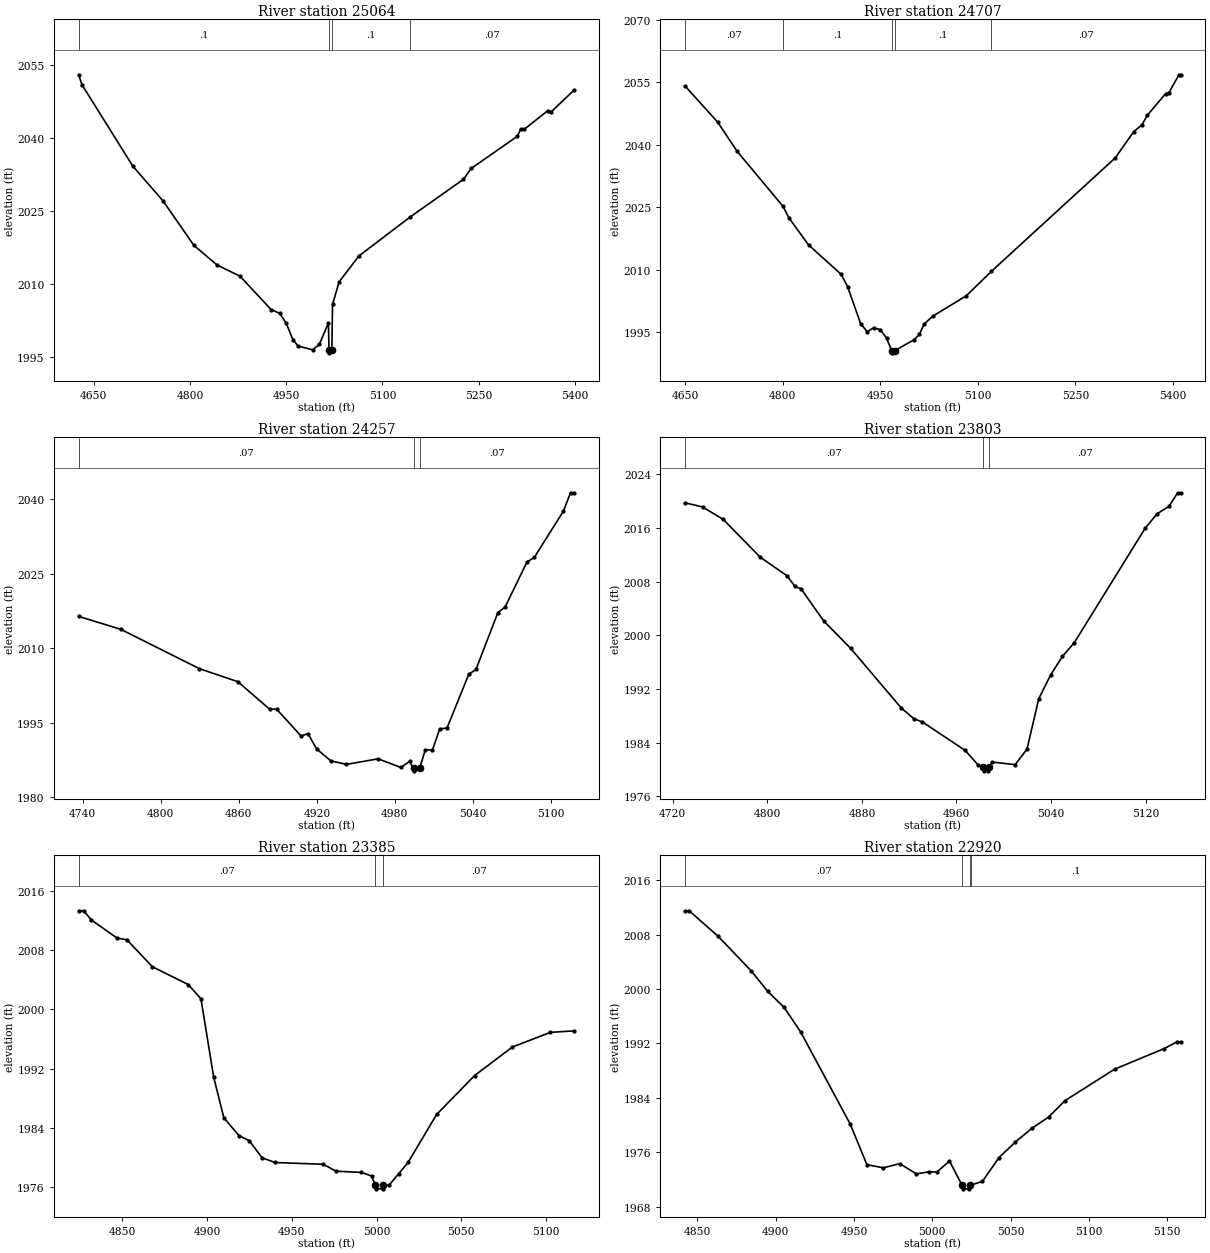
Type RM Length L Ch R = 1,25064,357,357,357
BEGIN DESCRIPTION:
Cypress Creek 2 53.0
END DESCRIPTION:
XS GIS Cut Line= 2
      1861779.90     13905160.35      1861959.23     13905911.13
#Sta/Elev= 30
  4626.7 2053.07  4631.9 2051.02  4710.9 2034.33  4758.1 2027.16  4806.3 2018.00
  4842.3 2013.98  4878.2 2011.66  4926.5 2004.82  4939.9 2004.04  4950.2 2001.96
  4960.5 1998.62  4968.6 1997.32  4991.3 1996.54  5001.6 1997.66  5015.8 2002.04
  5016.7 1996.42  5017.0 1995.92  5021.2 1996.42  5022.2 2005.86  5032.4 2010.50
  5063.3 2015.83  5143.3 2023.86  5226.2 2031.59  5238.1 2033.81  5310.0 2040.42
  5315.5 2041.96  5320.7 2041.83  5357.6 2045.72  5362.7 2045.45  5398.6 2049.93
#Mann=4,-1,0
  4626.7     0.1       0  5016.7    0.05       0  5021.2     0.1       0
  5143.3    0.07       0
Bank Sta=5016.7,5021.2
Exp/Cntr=0.3,0.1

Type RM Length L Ch R = 1,24707,450,450,450
BEGIN DESCRIPTION:
Cypress Creek 2 52.0
END DESCRIPTION:
XS GIS Cut Line= 3
      1861525.00     13905225.01      1861525.00     13905575.00
      1861625.00     13905975.00
#Sta/Elev= 30
  4649.6 2054.13  4699.6 2045.48  4729.6 2038.45  4800.3 2025.19  4809.6 2022.37
  4839.6 2015.92  4889.6 2008.88  4899.6 2005.89  4919.6 1997.03  4929.6 1995.08
  4939.6 1996.00  4949.6 1995.58  4959.6 1993.53  4967.3 1990.49  4967.6 1989.99
  4971.9 1990.49  5002.2 1993.19  5009.9 1994.43  5017.6 1996.93  5030.5 1998.80
  5082.1 2003.70  5120.7 2009.57  5311.4 2036.87  5339.7 2043.16  5352.6 2044.83
  5360.4 2047.07  5388.7 2052.28  5393.9 2052.54  5409.3 2056.84  5411.9 2056.84
#Mann=5,-1,0
  4649.6    0.07       0  4800.3     0.1       0  4967.3    0.05       0
  4971.9     0.1       0  5120.7    0.07       0
Bank Sta=4967.3,4971.9
Exp/Cntr=0.3,0.1

Type RM Length L Ch R = 1,24257,454,454,454
BEGIN DESCRIPTION:
Cypress Creek 2 51.0
END DESCRIPTION:
XS GIS Cut Line= 3
      1861225.01     13905474.97      1861125.00     13905725.00
      1861075.00     13905825.00
#Sta/Elev= 30
  4736.8 2016.41  4769.1 2013.81  4829.7 2005.86  4859.3 2003.23  4883.6 1997.70
  4889.0 1997.72  4907.8 1992.30  4913.2 1992.75  4919.9 1989.66  4930.7 1987.27
  4942.8 1986.56  4967.1 1987.68  4984.6 1985.95  4991.3 1987.15  4994.4 1985.76
  4994.7 1985.26  4999.0 1985.76  5003.4 1989.48  5008.9 1989.48  5014.5 1993.72
  5020.1 1993.89  5036.8 2004.71  5042.4 2005.72  5059.2 2017.15  5064.8 2018.30
  5081.6 2027.38  5087.2 2028.28  5109.5 2037.57  5115.1 2041.33  5117.9 2041.33
#Mann=3,-1,0
  4736.8    0.07       0  4994.4    0.05       0  4999.0    0.07       0
Bank Sta=4994.4,4999
Exp/Cntr=0.3,0.1

Type RM Length L Ch R = 1,23803,418,418,418
BEGIN DESCRIPTION:
Cypress Creek 2 50.0
END DESCRIPTION:
XS GIS Cut Line= 3
      1860825.01     13905324.98      1860725.00     13905575.00
      1860725.00     13905725.02
#Sta/Elev= 30
  4730.4 2019.78  4745.2 2019.15  4762.7 2017.30  4793.7 2011.71  4816.6 2008.90
  4823.3 2007.34  4828.7 2006.91  4847.6 2002.18  4870.4 1998.09  4913.5 1989.15
  4924.3 1987.55  4931.0 1987.13  4967.4 1982.86  4978.1 1980.74  4982.5 1980.32
  4982.9 1979.82  4986.9 1979.82  4987.2 1980.32  4990.3 1981.13  5009.7 1980.74
  5019.7 1983.06  5029.7 1990.59  5039.7 1994.12  5049.7 1996.88  5059.7 1998.92
  5119.7 2015.99  5129.7 2018.12  5139.7 2019.23  5147.2 2021.27  5149.7 2021.27
#Mann=3,-1,0
  4730.4    0.07       0  4982.5    0.05       0  4987.2    0.07       0
Bank Sta=4982.5,4987.2
Exp/Cntr=0.3,0.1

Type RM Length L Ch R = 1,23385,465,465,465
BEGIN DESCRIPTION:
Cypress Creek 2 49.0
END DESCRIPTION:
XS GIS Cut Line= 3
      1860474.99     13905225.02      1860375.00     13905375.00
      1860324.98     13905475.04
#Sta/Elev= 30
  4824.4 2013.33  4827.4 2013.33  4831.9 2012.09  4846.9 2009.66  4852.9 2009.40
  4867.9 2005.76  4889.0 2003.36  4896.5 2001.44  4904.0 1990.85  4910.0 1985.35
  4919.0 1982.92  4925.0 1982.26  4932.5 1979.95  4940.1 1979.31  4968.6 1979.07
  4976.1 1978.14  4991.1 1977.97  4997.1 1977.48  4999.2 1976.25  4999.6 1975.75
  5003.7 1975.75  5004.0 1976.25  5007.4 1976.25  5013.0 1977.77  5018.6 1979.32
  5035.4 1985.80  5057.8 1991.06  5080.1 1994.92  5102.5 1996.90  5116.5 1997.10
#Mann=3,-1,0
  4824.4    0.07       0  4999.2    0.05       0  5004.0    0.07       0
Bank Sta=4999.2,5004
Exp/Cntr=0.3,0.1

Type RM Length L Ch R = 1,22920,538,538,538
BEGIN DESCRIPTION:
Cypress Creek 2 48.0
END DESCRIPTION:
XS GIS Cut Line= 3
      1860025.00     13905025.00      1859975.00     13905175.00
      1859925.01     13905324.97
#Sta/Elev= 30
  4842.3 2011.52  4844.9 2011.52  4863.4 2007.76  4884.5 2002.67  4895.0 1999.66
  4905.5 1997.30  4916.1 1993.66  4947.7 1980.11  4958.3 1974.16  4968.8 1973.69
  4979.3 1974.31  4989.9 1972.80  4997.8 1973.10  5003.1 1973.10  5011.0 1974.69
  5019.1 1971.10  5019.4 1970.60  5023.5 1970.60  5023.9 1971.10  5024.7 1971.16
  5032.0 1971.69  5042.6 1975.20  5053.1 1977.50  5063.7 1979.53  5074.2 1981.15
  5084.7 1983.58  5116.4 1988.21  5148.0 1991.24  5155.9 1992.20  5158.5 1992.20
#Mann=4,-1,0
  4842.3    0.07       0  5019.1    0.05       0  5023.9    0.07       0
  5024.7     0.1       0
Bank Sta=5019.1,5023.9
Exp/Cntr=0.3,0.1

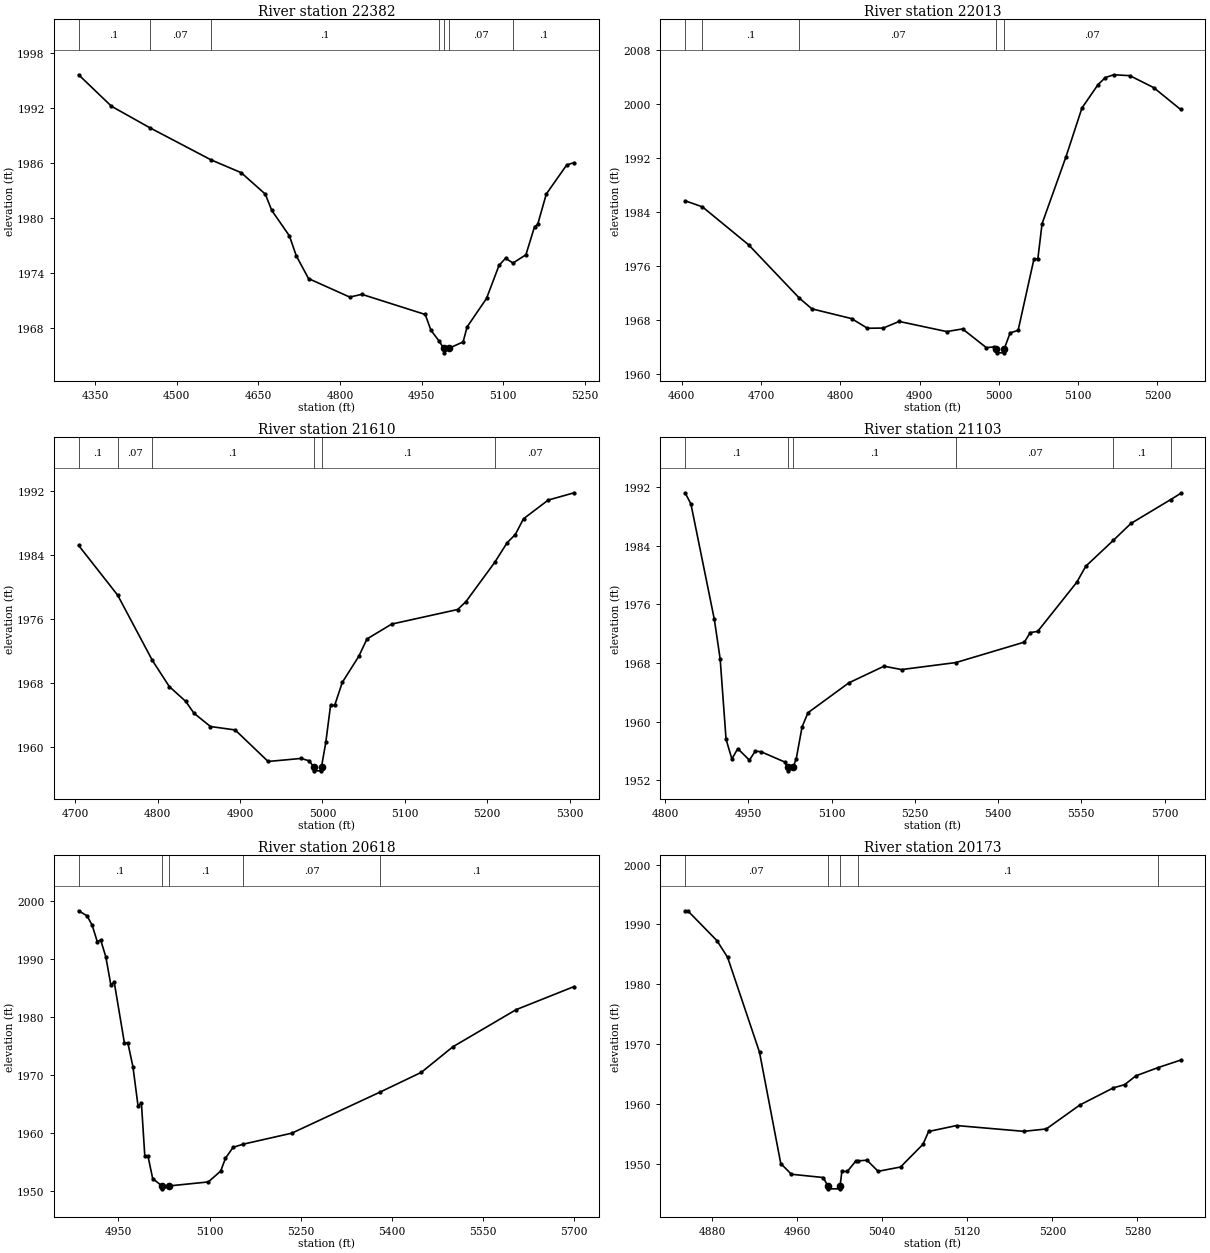
Type RM Length L Ch R = 1,22382,369,369,369
BEGIN DESCRIPTION:
Cypress Creek 2 47.0
END DESCRIPTION:
XS GIS Cut Line= 3
      1859200.85     13904469.31      1859522.76     13905095.14
      1859625.02     13905275.03
#Sta/Elev= 30
  4319.6 1995.64  4380.0 1992.20  4450.3 1989.86  4562.8 1986.35  4618.3 1984.95
  4662.6 1982.61  4674.6 1980.82  4707.0 1978.04  4719.6 1975.87  4742.1 1973.38
  4817.9 1971.36  4840.1 1971.66  4956.6 1969.46  4967.0 1967.74  4982.3 1966.54
  4990.4 1965.77  4990.9 1965.27  5000.1 1965.77  5026.2 1966.46  5033.5 1968.10
  5069.2 1971.21  5092.2 1974.82  5104.1 1975.60  5117.9 1975.08  5141.6 1975.98
  5157.5 1979.05  5163.2 1979.29  5179.1 1982.62  5216.6 1985.79  5230.3 1986.05
#Mann=7,-1,0
  4319.6     0.1       0  4450.3    0.07       0  4562.8     0.1       0
  4982.3    0.07       0  4990.4    0.05       0  5000.1    0.07       0
  5117.9     0.1       0
Bank Sta=4990.4,5000.1
Exp/Cntr=0.3,0.1

Type RM Length L Ch R = 1,22013,403,403,403
BEGIN DESCRIPTION:
Cypress Creek 2 46.0
END DESCRIPTION:
XS GIS Cut Line= 3
      1859175.00     13904775.05      1859175.00     13905175.00
      1859149.87     13905398.74
#Sta/Elev= 30
  4604.3 1985.64  4626.2 1984.73  4684.3 1979.13  4748.6 1971.20  4764.3 1969.63
  4814.3 1968.19  4834.3 1966.76  4854.3 1966.79  4874.3 1967.77  4934.3 1966.27
  4954.3 1966.66  4984.3 1963.89  4994.3 1964.00  4996.9 1963.62  4997.4 1963.12
  5006.1 1963.12  5006.6 1963.62  5014.3 1966.07  5024.4 1966.45  5044.3 1976.97
  5049.3 1977.06  5054.6 1982.24  5084.8 1992.16  5104.9 1999.37  5125.0 2002.80
  5134.3 2003.88  5145.1 2004.29  5165.3 2004.16  5195.4 2002.39  5229.4 1999.15
#Mann=5,-1,0
  4604.3    0.07       0  4626.2     0.1       0  4748.6    0.07       0
  4996.9    0.05       0  5006.6    0.07       0
Bank Sta=4996.9,5006.6
Exp/Cntr=0.3,0.1

Type RM Length L Ch R = 1,21610,507,507,507
BEGIN DESCRIPTION:
Cypress Creek 2 45.0
END DESCRIPTION:
XS GIS Cut Line= 3
      1858825.00     13904725.03      1858825.55     13905031.73
      1858827.52     13905326.52
#Sta/Elev= 30
  4704.1 1985.15  4751.5 1978.93  4793.6 1970.78  4814.1 1967.52  4834.1 1965.66
  4844.1 1964.18  4864.1 1962.52  4894.1 1962.09  4934.1 1958.15  4974.1 1958.53
  4984.1 1958.23  4989.2 1957.48  4989.7 1956.98  4998.4 1956.98  4998.9 1957.48
  5004.1 1960.53  5009.9 1965.16  5014.9 1965.16  5024.1 1968.03  5044.1 1971.28
  5054.1 1973.46  5084.1 1975.32  5164.1 1977.14  5174.1 1978.11  5209.2 1983.04
  5224.1 1985.47  5234.1 1986.51  5244.1 1988.48  5274.1 1990.82  5305.6 1991.73
#Mann=6,-1,0
  4704.1     0.1       0  4751.5    0.07       0  4793.6     0.1       0
  4989.2    0.05       0  4998.9     0.1       0  5209.2    0.07       0
Bank Sta=4989.2,4998.9
Exp/Cntr=0.3,0.1

Type RM Length L Ch R = 1,21103,485,485,485
BEGIN DESCRIPTION:
Cypress Creek 2 44.0
END DESCRIPTION:
XS GIS Cut Line= 4
      1858375.00     13904625.00      1858425.00     13904775.00
      1858575.00     13905225.00      1858803.14     13905350.64
#Sta/Elev= 30
  4836.0 1991.24  4846.5 1989.71  4888.7 1973.95  4899.2 1968.56  4909.8 1957.59
  4920.3 1954.91  4930.9 1956.32  4951.9 1954.75  4962.5 1955.99  4973.0 1955.89
  5015.2 1954.51  5020.8 1953.79  5021.3 1953.29  5030.7 1953.79  5036.3 1954.96
  5046.8 1959.29  5057.4 1961.22  5131.1 1965.30  5194.4 1967.57  5226.0 1967.11
  5324.0 1968.07  5447.4 1970.86  5457.9 1972.16  5471.3 1972.32  5541.8 1979.03
  5557.9 1981.21  5607.8 1984.76  5639.3 1987.05  5710.9 1990.31  5728.9 1991.15
#Mann=6,-1,0
  4836.0     0.1       0  5020.8    0.05       0  5030.7     0.1       0
  5324.0    0.07       0  5607.8     0.1       0  5710.9    0.07       0
Bank Sta=5020.8,5030.7
Exp/Cntr=0.3,0.1

Type RM Length L Ch R = 1,20618,445,445,445
BEGIN DESCRIPTION:
Cypress Creek 2 43.0
END DESCRIPTION:
XS GIS Cut Line= 3
      1858024.98     13904575.04      1857975.00     13904675.00
      1857842.52     13905366.57
#Sta/Elev= 30
  4884.5 1998.39  4898.4 1997.51  4906.8 1995.90  4915.2 1993.06  4920.8 1993.35
  4929.2 1990.48  4937.6 1985.59  4943.1 1986.08  4959.9 1975.58  4965.5 1975.63
  4973.9 1971.51  4982.3 1964.76  4987.9 1965.20  4993.5 1956.04  4998.8 1956.04
  5006.4 1952.23  5021.6 1950.95  5022.1 1950.45  5033.1 1950.95  5098.1 1951.64
  5118.4 1953.52  5126.3 1955.72  5138.8 1957.61  5155.9 1958.16  5235.5 1960.05
  5381.4 1967.16  5448.7 1970.53  5500.7 1974.94  5604.8 1981.34  5700.4 1985.33
#Mann=5,-1,0
  4884.5     0.1       0  5021.6    0.05       0  5033.1     0.1       0
  5155.9    0.07       0  5381.4     0.1       0
Bank Sta=5021.6,5033.1
Exp/Cntr=0.3,0.1

Type RM Length L Ch R = 1,20173,466,466,466
BEGIN DESCRIPTION:
Cypress Creek 2 42.0
END DESCRIPTION:
XS GIS Cut Line= 3
      1857575.00     13904574.99      1857575.00     13904725.00
      1857674.99     13905024.96
#Sta/Elev= 30
  4854.5 1992.29  4857.0 1992.29  4884.5 1987.29  4894.5 1984.50  4924.5 1968.65
  4944.5 1950.04  4954.5 1948.25  4984.5 1947.70  4988.7 1946.31  4989.2 1945.81
  4999.8 1945.81  5000.3 1946.31  5002.0 1948.72  5007.1 1948.72  5015.1 1950.45
  5017.0 1950.48  5025.6 1950.60  5036.1 1948.74  5057.2 1949.46  5078.3 1953.26
  5083.6 1955.40  5109.9 1956.39  5173.2 1955.42  5194.3 1955.82  5225.9 1959.83
  5257.5 1962.70  5268.0 1963.22  5278.6 1964.70  5299.5 1966.08  5320.7 1967.33
#Mann=5,-1,0
  4854.5    0.07       0  4988.7    0.05       0  5000.3    0.07       0
  5017.0     0.1       0  5299.5    0.07       0
Bank Sta=4988.7,5000.3
Exp/Cntr=0.3,0.1

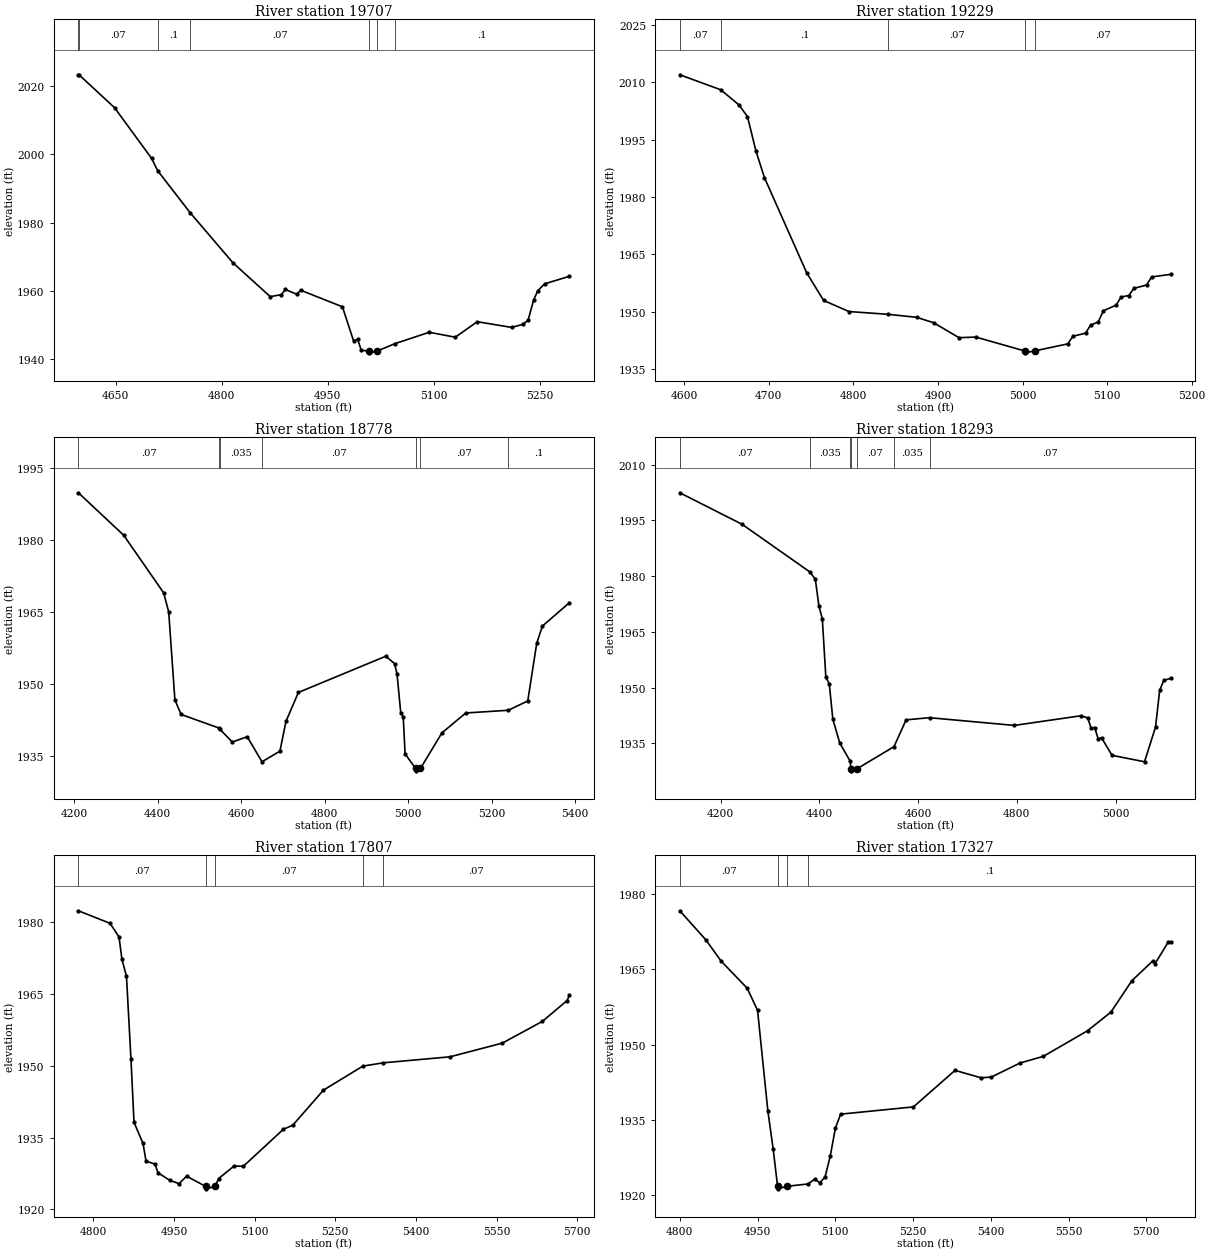
Type RM Length L Ch R = 1,19707,478,478,478
BEGIN DESCRIPTION:
Cypress Creek 2 41.0
END DESCRIPTION:
XS GIS Cut Line= 3
      1857325.00     13904325.00      1857125.00     13904675.00
      1856974.98     13904925.04
#Sta/Elev= 30
  4597.0 2023.39  4597.9 2023.39  4648.1 2013.74  4700.7 1998.82  4709.2 1995.22
  4755.1 1982.91  4815.8 1968.18  4868.4 1958.28  4884.2 1958.85  4890.0 1960.37
  4905.8 1958.99  4911.6 1960.15  4970.6 1955.30  4986.4 1945.27  4992.2 1945.73
  4997.2 1942.55  5007.9 1942.28  5008.4 1941.78  5019.5 1942.28  5045.0 1944.48
  5093.4 1947.82  5130.3 1946.36  5161.4 1950.92  5210.0 1949.24  5225.6 1950.13
  5233.3 1951.32  5241.1 1957.24  5247.0 1960.00  5256.7 1962.03  5291.7 1964.24
#Mann=7,-1,0
  4597.0     0.1       0  4597.9    0.07       0  4709.2     0.1       0
  4755.1    0.07       0  5007.9    0.05       0  5019.5    0.07       0
  5045.0     0.1       0
Bank Sta=5007.9,5019.5
Exp/Cntr=0.3,0.1

Type RM Length L Ch R = 1,19229,451,451,451
BEGIN DESCRIPTION:
Cypress Creek 2 40.0
END DESCRIPTION:
XS GIS Cut Line= 3
      1856675.00     13904375.02      1856675.00     13904775.00
      1856825.04     13904875.03
#Sta/Elev= 30
  4594.9 2011.90  4643.3 2007.99  4664.9 2004.02  4674.9 2000.97  4684.9 1992.00
  4694.9 1985.08  4744.9 1960.20  4764.9 1952.99  4794.9 1950.10  4841.4 1949.37
  4874.9 1948.59  4894.9 1947.18  4924.9 1943.28  4944.9 1943.43  5002.5 1939.82
  5003.0 1939.32  5014.2 1939.82  5053.5 1941.66  5059.5 1943.64  5074.5 1944.46
  5080.5 1946.57  5089.5 1947.37  5095.5 1950.29  5110.6 1951.76  5116.6 1953.91
  5125.6 1954.27  5131.6 1956.15  5146.6 1957.02  5152.6 1959.12  5175.2 1959.82
#Mann=5,-1,0
  4594.9    0.07       0  4643.3     0.1       0  4841.4    0.07       0
  5002.5    0.05       0  5014.2    0.07       0
Bank Sta=5002.5,5014.2
Exp/Cntr=0.3,0.1

Type RM Length L Ch R = 1,18778,485,485,485
BEGIN DESCRIPTION:
Cypress Creek 2 39.0
END DESCRIPTION:
XS GIS Cut Line= 3
      1855676.38     13904581.40      1856325.00     13905025.00
      1856624.99     13905274.99
#Sta/Elev= 30
  4210.1 1989.78  4318.7 1980.94  4414.3 1968.97  4426.5 1964.98  4441.3 1946.69
  4456.2 1943.66  4546.2 1940.86  4548.8 1940.61  4578.8 1937.92  4614.7 1939.02
  4650.0 1933.81  4693.0 1936.03  4707.4 1942.21  4737.2 1948.24  4946.5 1955.77
  4967.5 1954.25  4973.5 1952.14  4982.4 1944.04  4988.4 1943.16  4992.9 1935.45
  5018.0 1932.43  5018.5 1931.93  5029.7 1932.43  5081.2 1939.84  5138.4 1943.97
  5240.2 1944.53  5286.8 1946.47  5308.3 1958.50  5322.0 1962.06  5386.4 1966.90
#Mann=7,-1,0
  4210.1    0.07       0  4546.2     0.1       0  4548.8   0.035       0
  4650.0    0.07       0  5018.0    0.05       0  5029.7    0.07       0
  5240.2     0.1       0
Bank Sta=5018,5029.7
Exp/Cntr=0.3,0.1

Type RM Length L Ch R = 1,18293,486,486,486
BEGIN DESCRIPTION:
Cypress Creek 2 38.0
END DESCRIPTION:
XS GIS Cut Line= 3
      1855489.11     13904762.52      1856125.00     13905375.00
      1856175.00     13905475.01
#Sta/Elev= 30
  4117.1 2002.42  4243.3 1993.94  4380.2 1981.16  4391.7 1979.16  4398.9 1972.00
  4405.8 1968.55  4413.0 1952.84  4420.0 1950.98  4427.2 1941.46  4441.3 1935.06
  4462.4 1930.19  4463.8 1928.11  4464.3 1927.61  4475.5 1928.11  4551.1 1934.12
  4575.6 1941.33  4623.1 1941.91  4794.8 1939.83  4929.4 1942.42  4943.5 1941.88
  4950.5 1939.09  4957.7 1939.24  4964.6 1936.28  4971.8 1936.45  4992.9 1931.78
  5058.7 1930.05  5081.0 1939.39  5089.4 1949.32  5097.8 1951.95  5111.8 1952.51
#Mann=7,-1,0
  4117.1    0.07       0  4380.2   0.035       0  4462.4    0.07       0
  4463.8    0.05       0  4475.5    0.07       0  4551.1   0.035       0
  4623.1    0.07       0
Bank Sta=4463.8,4475.5
Exp/Cntr=0.3,0.1

Type RM Length L Ch R = 1,17807,480,480,480
BEGIN DESCRIPTION:
Cypress Creek 2 37.0
END DESCRIPTION:
XS GIS Cut Line= 3
      1855575.00     13905275.01      1855675.00     13905475.00
      1856301.55     13905762.82
#Sta/Elev= 30
  4772.2 1982.36  4830.9 1979.75  4847.7 1976.92  4853.2 1972.22  4861.6 1968.69
  4870.0 1951.36  4875.6 1938.20  4892.4 1933.78  4898.0 1930.10  4914.7 1929.47
  4920.3 1927.65  4942.7 1926.06  4959.5 1925.39  4973.4 1926.95  5009.1 1924.81
  5009.6 1924.31  5026.5 1924.81  5033.0 1926.46  5061.8 1929.08  5079.0 1929.02
  5153.4 1936.74  5170.9 1937.59  5227.9 1944.91  5301.2 1949.93  5339.2 1950.62
  5463.2 1951.87  5560.6 1954.73  5635.1 1959.26  5681.1 1963.62  5685.3 1964.69
#Mann=5,-1,0
  4772.2    0.07       0  5009.1    0.05       0  5026.5    0.07       0
  5301.2     0.1       0  5339.2    0.07       0
Bank Sta=5009.1,5026.5
Exp/Cntr=0.3,0.1

Type RM Length L Ch R = 1,17327,453,453,453
BEGIN DESCRIPTION:
Cypress Creek 2 36.0
END DESCRIPTION:
XS GIS Cut Line= 3
      1855374.98     13905925.00      1855575.00     13905925.00
      1856319.98     13905867.69
#Sta/Elev= 30
  4800.0 1976.70  4850.0 1970.93  4880.0 1966.64  4930.0 1961.26  4950.0 1956.85
  4970.0 1936.70  4980.0 1929.29  4988.7 1921.76  4989.2 1921.26  5006.4 1921.76
  5047.3 1922.23  5060.2 1923.18  5070.2 1922.48  5080.3 1923.63  5090.3 1927.81
  5100.3 1933.41  5110.3 1936.15  5250.8 1937.60  5331.0 1944.88  5381.1 1943.40
  5401.2 1943.55  5456.3 1946.34  5501.5 1947.68  5586.7 1952.78  5631.9 1956.51
  5672.0 1962.73  5712.1 1966.66  5717.1 1966.18  5742.2 1970.44  5747.2 1970.44
#Mann=4,-1,0
  4800.0    0.07       0  4988.7    0.05       0  5006.4    0.07       0
  5047.3     0.1       0
Bank Sta=4988.7,5006.4
Exp/Cntr=0.3,0.1

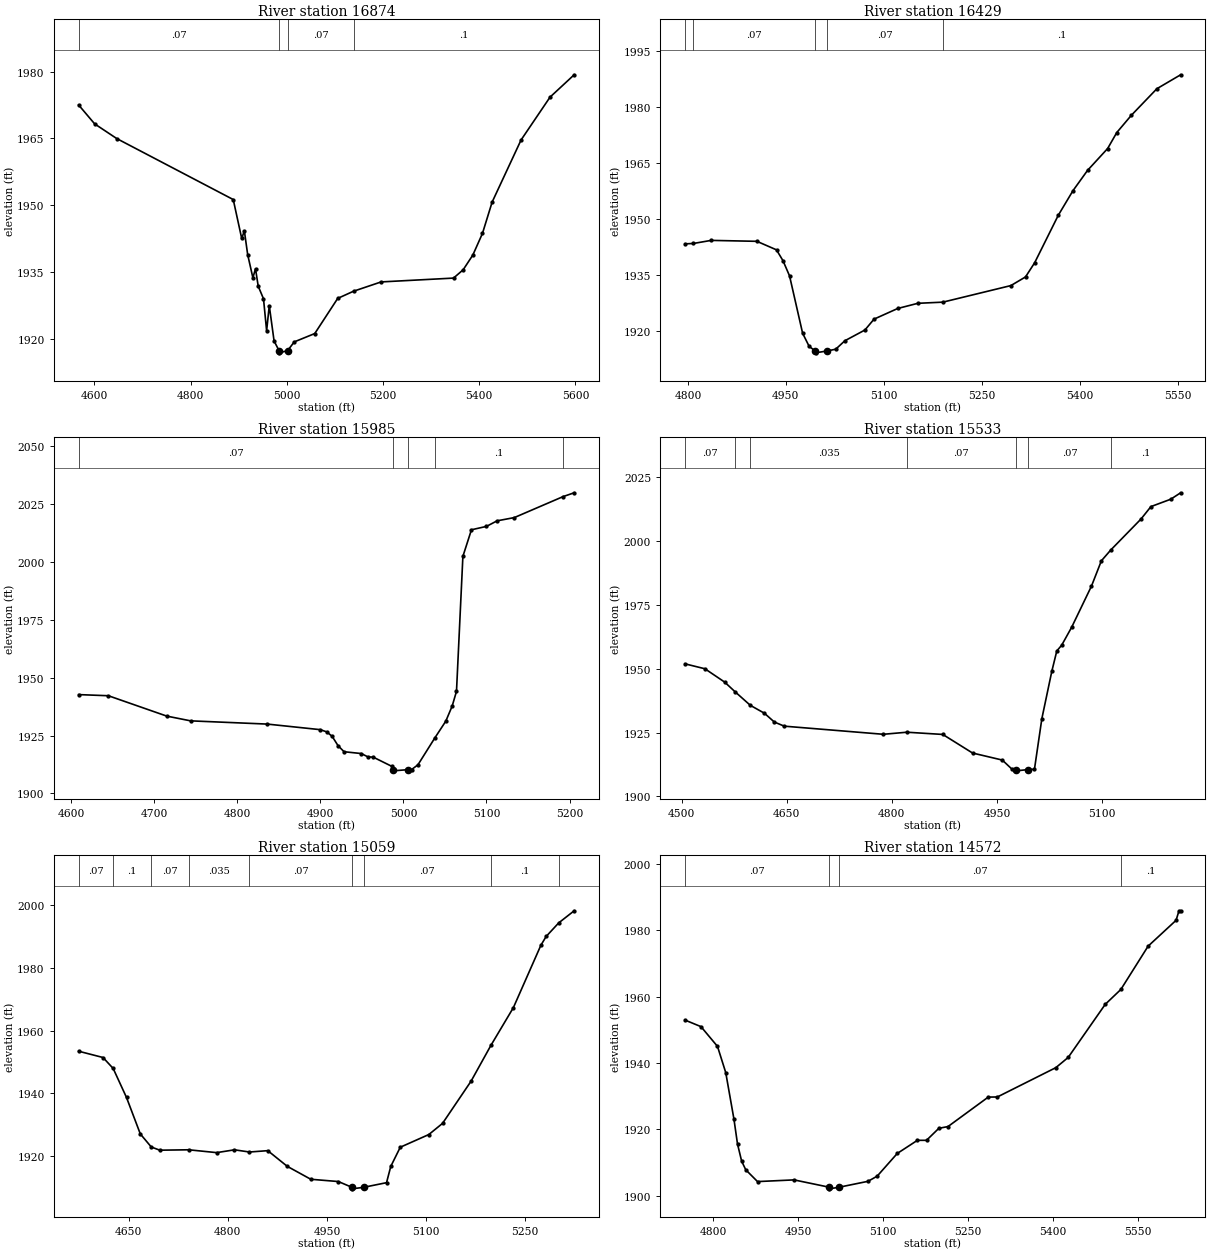
Type RM Length L Ch R = 1,16874,445,445,445
BEGIN DESCRIPTION:
Cypress Creek 2 35.0
END DESCRIPTION:
XS GIS Cut Line= 3
      1855334.65     13906148.74      1855725.00     13906325.00
      1856325.02     13906275.00
#Sta/Elev= 30
  4567.1 1972.51  4600.4 1968.27  4646.4 1964.97  4888.6 1951.28  4906.2 1942.55
  4911.7 1944.25  4918.6 1938.92  4929.4 1933.73  4934.9 1935.74  4940.5 1931.83
  4951.5 1929.01  4958.0 1921.83  4963.5 1927.46  4973.5 1919.53  4983.8 1917.37
  4984.3 1916.87  5001.6 1917.37  5015.5 1919.33  5058.1 1921.20  5105.8 1929.09
  5138.7 1930.70  5196.1 1932.79  5346.6 1933.65  5366.7 1935.52  5386.8 1938.82
  5406.8 1943.68  5426.9 1950.71  5487.1 1964.66  5547.3 1974.27  5597.5 1979.29
#Mann=4,-1,0
  4567.1    0.07       0  4983.8    0.05       0  5001.6    0.07       0
  5138.7     0.1       0
Bank Sta=4983.8,5001.6
Exp/Cntr=0.3,0.1

Type RM Length L Ch R = 1,16429,444,444,444
BEGIN DESCRIPTION:
Cypress Creek 2 34.0
END DESCRIPTION:
XS GIS Cut Line= 3
      1855775.04     13906675.00      1855975.00     13906675.00
      1856475.02     13906424.99
#Sta/Elev= 30
  4795.7 1943.36  4808.5 1943.47  4835.7 1944.29  4905.7 1944.04  4935.7 1941.76
  4945.7 1938.84  4955.7 1934.79  4975.7 1919.47  4985.7 1915.96  4995.0 1914.73
  4995.5 1914.23  5013.0 1914.73  5026.4 1915.20  5040.4 1917.46  5071.1 1920.33
  5085.1 1923.24  5121.4 1926.09  5152.2 1927.47  5190.5 1927.78  5294.7 1932.21
  5317.1 1934.52  5331.1 1938.31  5367.4 1951.04  5389.8 1957.58  5412.1 1963.00
  5442.9 1968.85  5456.9 1973.12  5479.2 1977.73  5518.3 1984.83  5554.7 1988.56
#Mann=5,-1,0
  4795.7   0.035       0  4808.5    0.07       0  4995.0    0.05       0
  5013.0    0.07       0  5190.5     0.1       0
Bank Sta=4995,5013
Exp/Cntr=0.3,0.1

Type RM Length L Ch R = 1,15985,452,452,452
BEGIN DESCRIPTION:
Cypress Creek 2 33.0
END DESCRIPTION:
XS GIS Cut Line= 3
      1855824.97     13906774.98      1856125.00     13907025.00
      1856175.00     13907224.99
#Sta/Elev= 30
  4608.9 1942.73  4644.7 1942.24  4715.0 1933.44  4743.7 1931.39  4836.1 1929.99
  4899.9 1927.58  4907.7 1926.62  4914.2 1924.68  4921.3 1920.65  4928.5 1918.05
  4949.3 1917.26  4957.1 1915.84  4963.7 1915.69  4985.8 1911.77  4987.1 1910.29
  4987.6 1909.79  5005.2 1910.29  5009.8 1910.33  5017.5 1912.41  5038.0 1924.11
  5051.0 1931.24  5058.7 1937.78  5063.9 1944.14  5071.6 2002.45  5081.9 2013.94
  5100.0 2015.41  5112.8 2017.81  5133.5 2019.21  5192.4 2028.30  5205.6 2029.93
#Mann=5,-1,0
  4608.9    0.07       0  4987.1    0.05       0  5005.2    0.07       0
  5038.0     0.1       0  5192.4    0.07       0
Bank Sta=4987.1,5005.2
Exp/Cntr=0.3,0.1

Type RM Length L Ch R = 1,15533,474,474,474
BEGIN DESCRIPTION:
Cypress Creek 2 32.0
END DESCRIPTION:
XS GIS Cut Line= 3
      1855424.98     13906874.98      1855775.00     13907225.00
      1855924.97     13907374.97
#Sta/Elev= 30
  4505.1 1951.88  4533.4 1949.96  4561.7 1944.71  4576.4 1940.96  4598.2 1935.64
  4618.3 1932.55  4632.4 1929.11  4646.6 1927.49  4788.0 1924.31  4821.5 1925.12
  4872.8 1924.25  4915.3 1916.97  4957.7 1914.22  4971.8 1910.59  4976.9 1910.50
  4977.4 1910.00  4995.0 1910.50  5003.6 1910.61  5014.2 1930.48  5028.4 1949.00
  5035.5 1956.95  5042.5 1959.20  5056.7 1966.22  5085.0 1982.34  5099.1 1992.23
  5112.5 1996.46  5155.7 2008.60  5169.8 2013.45  5198.1 2016.34  5212.2 2018.86
#Mann=7,-1,0
  4505.1    0.07       0  4576.4     0.1       0  4598.2   0.035       0
  4821.5    0.07       0  4976.9    0.05       0  4995.0    0.07       0
  5112.5     0.1       0
Bank Sta=4976.9,4995
Exp/Cntr=0.3,0.1

Type RM Length L Ch R = 1,15059,487,487,487
BEGIN DESCRIPTION:
Cypress Creek 2 31.0
END DESCRIPTION:
XS GIS Cut Line= 3
      1855124.98     13907074.97      1855375.00     13907425.00
      1855624.99     13907624.99
#Sta/Elev= 30
  4574.1 1953.40  4611.0 1951.39  4626.4 1947.89  4646.6 1938.61  4667.5 1926.96
  4684.1 1922.79  4697.0 1921.77  4740.7 1921.90  4783.1 1920.99  4810.1 1921.89
  4832.7 1921.19  4860.5 1921.62  4890.0 1916.61  4925.6 1912.48  4967.4 1911.75
  4987.8 1909.92  4988.3 1909.42  5005.9 1909.92  5040.3 1911.39  5046.7 1916.58
  5061.1 1922.72  5104.3 1926.77  5125.1 1930.34  5168.3 1943.83  5198.4 1955.29
  5232.4 1967.35  5274.0 1987.26  5282.0 1990.08  5301.0 1994.41  5324.4 1998.28
#Mann=9,-1,0
  4574.1    0.07       0  4626.4     0.1       0  4684.1    0.07       0
  4740.7   0.035       0  4832.7    0.07       0  4987.8    0.05       0
  5005.9    0.07       0  5198.4     0.1       0  5301.0    0.07       0
Bank Sta=4987.8,5005.9
Exp/Cntr=0.3,0.1

Type RM Length L Ch R = 1,14572,451,451,451
BEGIN DESCRIPTION:
Cypress Creek 2 30.0
END DESCRIPTION:
XS GIS Cut Line= 3
      1854775.01     13907325.02      1854925.00     13907525.00
      1855475.02     13907825.01
#Sta/Elev= 30
  4749.8 1952.94  4777.9 1950.97  4807.1 1945.01  4821.7 1937.10  4836.2 1923.06
  4842.5 1915.56  4849.8 1910.39  4857.1 1907.78  4877.9 1904.22  4942.5 1904.73
  5004.5 1902.53  5005.0 1902.03  5022.6 1902.53  5073.3 1904.30  5089.5 1905.85
  5125.1 1912.71  5160.7 1916.67  5176.8 1916.67  5198.6 1920.29  5214.8 1920.82
  5286.0 1929.71  5302.1 1929.75  5405.6 1938.60  5427.4 1941.68  5492.9 1957.69
  5520.6 1962.20  5568.8 1975.26  5618.2 1983.05  5623.4 1985.93  5626.3 1985.93
#Mann=4,-1,0
  4749.8    0.07       0  5004.5    0.05       0  5022.6    0.07       0
  5520.6     0.1       0
Bank Sta=5004.5,5022.6
Exp/Cntr=0.3,0.1

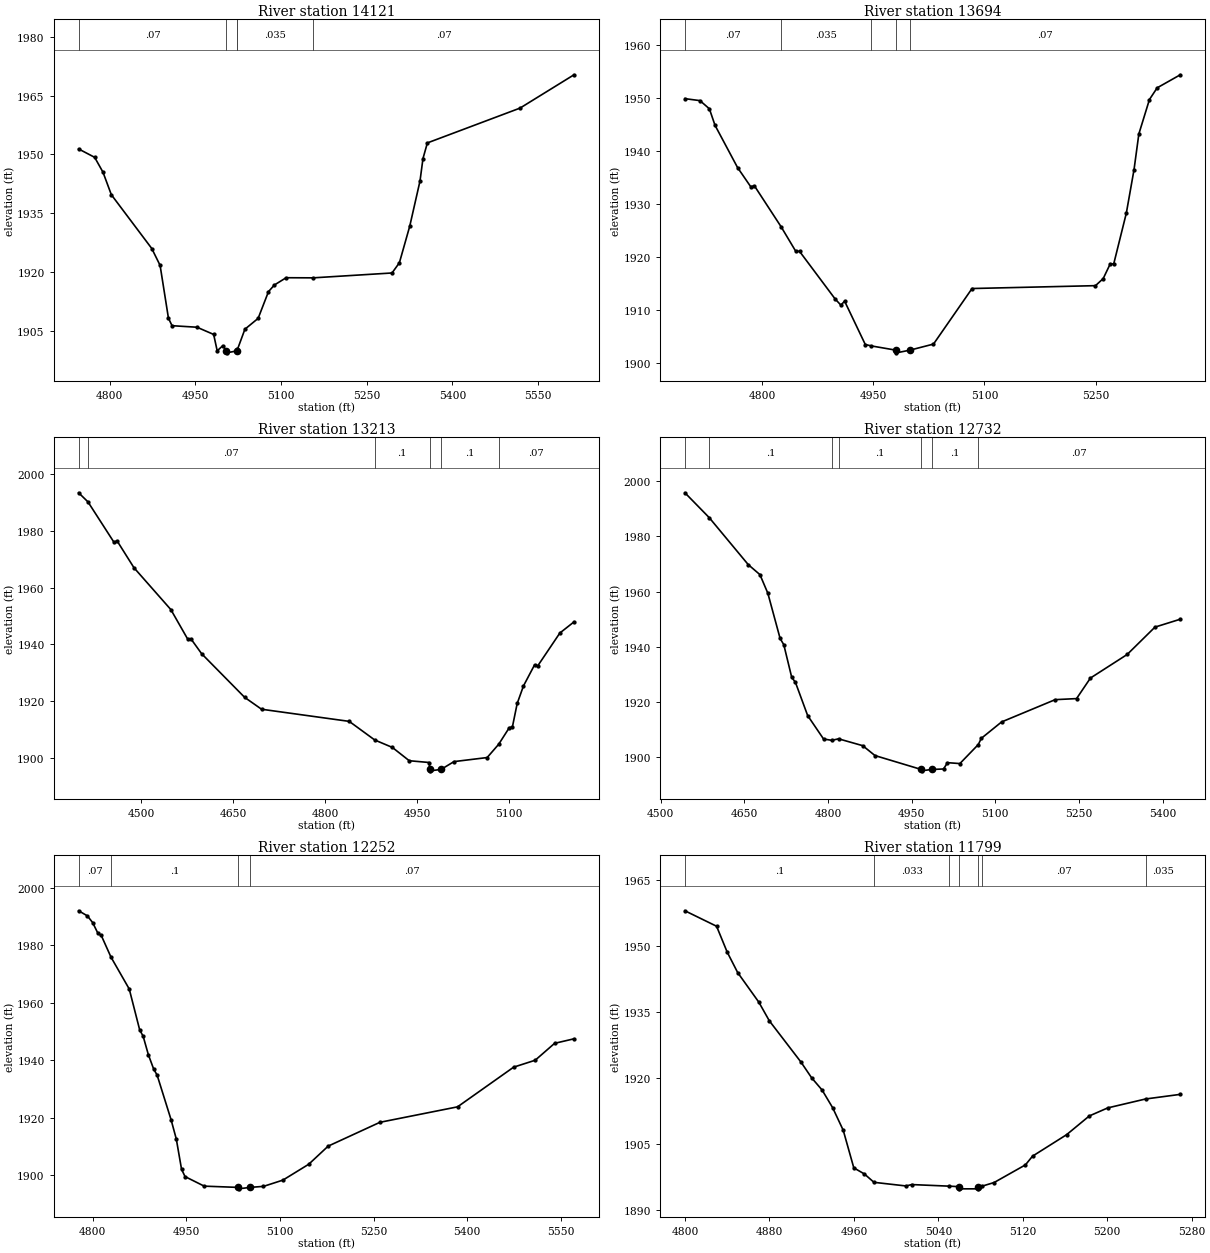
Type RM Length L Ch R = 1,14121,427,427,427
BEGIN DESCRIPTION:
Cypress Creek 2 29.0
END DESCRIPTION:
XS GIS Cut Line= 4
      1854424.99     13907524.99      1854575.00     13907725.00
      1854675.00     13908125.00      1854720.10     13908325.27
#Sta/Elev= 30
  4745.4 1951.39  4773.5 1949.25  4788.1 1945.45  4802.7 1939.72  4873.5 1926.01
  4888.1 1921.70  4902.7 1908.25  4909.0 1906.33  4952.7 1905.94  4981.9 1904.10
  4988.1 1899.92  4998.0 1901.25  5004.2 1899.91  5004.7 1899.41  5022.7 1899.91
  5023.6 1900.29  5036.6 1905.43  5059.8 1908.20  5077.9 1915.01  5088.2 1916.70
  5108.8 1918.56  5156.2 1918.53  5294.3 1919.77  5307.2 1922.38  5325.3 1931.69
  5343.3 1943.23  5348.5 1948.95  5356.2 1952.93  5518.4 1961.80  5613.0 1970.30
#Mann=5,-1,0
  4745.4    0.07       0  5004.2    0.05       0  5022.7    0.07       0
  5023.6   0.035       0  5156.2    0.07       0
Bank Sta=5004.2,5022.7
Exp/Cntr=0.3,0.1

Type RM Length L Ch R = 1,13694,481,481,481
BEGIN DESCRIPTION:
Cypress Creek 2 28.0
END DESCRIPTION:
XS GIS Cut Line= 3
      1854275.00     13907574.99      1854225.00     13907875.00
      1854325.01     13908225.04
#Sta/Elev= 30
  4695.9 1949.83  4716.2 1949.46  4728.9 1947.92  4736.5 1944.81  4766.9 1936.85
  4784.6 1933.25  4789.7 1933.39  4825.6 1925.70  4845.4 1921.07  4850.5 1921.06
  4898.7 1912.05  4906.3 1910.92  4911.3 1911.67  4939.2 1903.50  4947.5 1903.23
  4980.7 1902.43  4981.2 1901.93  4999.2 1902.43  5031.2 1903.58  5083.2 1914.05
  5249.7 1914.59  5260.1 1915.92  5269.2 1918.58  5274.4 1918.74  5291.3 1928.25
  5301.7 1936.46  5308.2 1943.18  5322.5 1949.67  5332.9 1951.87  5364.1 1954.33
#Mann=5,-1,0
  4695.9    0.07       0  4825.6   0.035       0  4947.5    0.07       0
  4980.7    0.05       0  4999.2    0.07       0
Bank Sta=4980.7,4999.2
Exp/Cntr=0.3,0.1

Type RM Length L Ch R = 1,13213,481,481,481
BEGIN DESCRIPTION:
Cypress Creek 2 27.0
END DESCRIPTION:
XS GIS Cut Line= 3
      1853725.00     13907374.99      1853775.00     13907975.00
      1853824.99     13908174.95
#Sta/Elev= 30
  4397.9 1993.45  4413.1 1990.25  4455.6 1975.97  4460.6 1976.49  4488.2 1966.99
  4548.4 1952.21  4576.0 1941.74  4581.0 1941.93  4598.6 1936.64  4668.8 1921.23
  4696.4 1917.04  4839.4 1912.76  4881.0 1906.19  4909.7 1903.57  4937.3 1898.87
  4969.9 1898.24  4970.7 1895.80  4971.2 1895.30  4989.2 1895.80  5010.3 1898.56
  5064.4 1899.99  5083.2 1904.67  5100.5 1910.53  5105.6 1910.80  5113.4 1919.07
  5123.7 1925.29  5141.7 1932.68  5146.9 1932.34  5183.0 1943.94  5206.1 1947.88
#Mann=6,-1,0
  4397.9     0.1       0  4413.1    0.07       0  4881.0     0.1       0
  4970.7    0.05       0  4989.2     0.1       0  5083.2    0.07       0
Bank Sta=4970.7,4989.2
Exp/Cntr=0.3,0.1

Type RM Length L Ch R = 1,12732,480,480,480
BEGIN DESCRIPTION:
Cypress Creek 2 26.0
END DESCRIPTION:
XS GIS Cut Line= 3
      1853025.00     13907625.00      1853325.00     13907975.00
      1853475.01     13908375.02
#Sta/Elev= 30
  4543.6 1995.78  4587.1 1986.80  4657.2 1969.76  4678.1 1966.15  4692.3 1959.41
  4714.3 1943.03  4720.9 1940.78  4735.1 1928.95  4741.7 1927.19  4763.7 1915.12
  4792.2 1906.64  4807.0 1906.17  4819.1 1906.71  4862.4 1904.23  4884.4 1900.65
  4967.3 1895.62  4967.8 1895.12  4985.8 1895.62  5007.3 1895.79  5014.4 1898.08
  5036.6 1897.75  5069.7 1904.65  5074.9 1906.86  5111.4 1912.82  5207.5 1920.89
  5245.8 1921.27  5270.7 1928.71  5336.6 1937.25  5386.4 1947.15  5431.8 1950.01
#Mann=7,-1,0
  4543.6    0.07       0  4587.1     0.1       0  4807.0    0.07       0
  4819.1     0.1       0  4967.3    0.05       0  4985.8     0.1       0
  5069.7    0.07       0
Bank Sta=4967.3,4985.8
Exp/Cntr=0.3,0.1

Type RM Length L Ch R = 1,12252,453,453,453
BEGIN DESCRIPTION:
Cypress Creek 2 25.0
END DESCRIPTION:
XS GIS Cut Line= 3
      1852775.00     13907775.00      1852875.00     13907975.00
      1853025.00     13908525.00
#Sta/Elev= 30
  4777.3 1992.09  4791.3 1990.32  4799.7 1988.00  4808.0 1984.34  4813.6 1983.48
  4829.2 1975.92  4858.4 1964.83  4875.1 1950.61  4880.7 1948.36  4889.1 1941.89
  4897.5 1936.96  4903.1 1934.81  4925.4 1919.30  4933.8 1912.56  4942.2 1902.03
  4947.8 1899.47  4978.5 1896.14  5033.1 1895.70  5033.6 1895.20  5051.7 1895.70
  5073.5 1896.06  5104.6 1898.24  5146.0 1903.77  5177.1 1910.08  5260.0 1918.38
  5384.4 1923.77  5474.3 1937.60  5508.8 1940.01  5539.9 1945.90  5571.0 1947.48
#Mann=4,-1,0
  4777.3    0.07       0  4829.2     0.1       0  5033.1    0.05       0
  5051.7    0.07       0
Bank Sta=5033.1,5051.7
Exp/Cntr=0.3,0.1

Type RM Length L Ch R = 1,11799,433,433,433
BEGIN DESCRIPTION:
Cypress Creek 2 24.0
END DESCRIPTION:
XS GIS Cut Line= 3
      1852475.00     13907924.96      1852475.00     13908125.00
      1852575.00     13908375.00
#Sta/Elev= 30
  4799.9 1957.91  4829.9 1954.40  4839.9 1948.56  4849.9 1943.88  4869.9 1937.18
  4879.9 1932.93  4909.9 1923.56  4919.9 1920.02  4929.9 1917.22  4939.9 1913.20
  4949.9 1908.09  4959.9 1899.57  4969.9 1898.19  4979.0 1896.29  5009.4 1895.46
  5014.7 1895.78  5050.2 1895.42  5059.3 1895.31  5059.8 1894.81  5077.4 1894.81
  5077.9 1895.31  5080.9 1895.38  5092.8 1896.24  5122.5 1900.25  5129.2 1902.22
  5161.5 1907.10  5183.0 1911.35  5200.5 1913.18  5236.3 1915.20  5269.2 1916.25
#Mann=7,-1,0
  4799.9     0.1       0  4979.0   0.033       0  5050.2     0.1       0
  5059.3   0.033       0  5077.9     0.1       0  5080.9    0.07       0
  5236.3   0.035       0
Bank Sta=5059.3,5077.9
Exp/Cntr=0.3,0.1