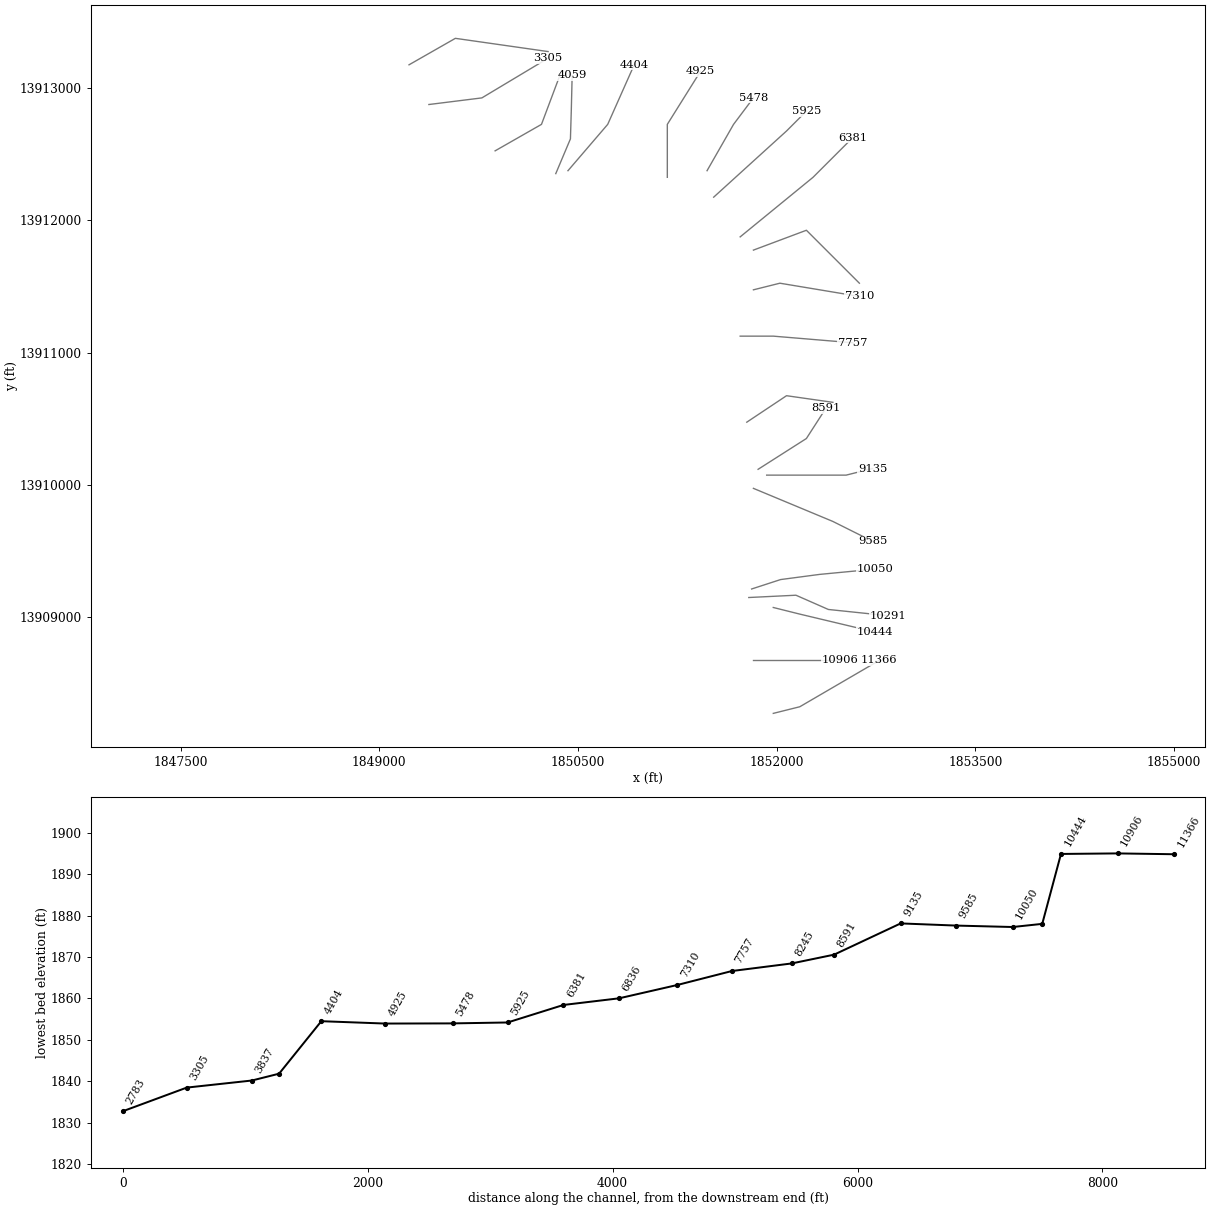
HEC-RAS study Cypress Creek 2.prj: Cypress Creek 2 Base Level Engineering

--- Cypress Creek 2.g01 (geometry) --- (continued)

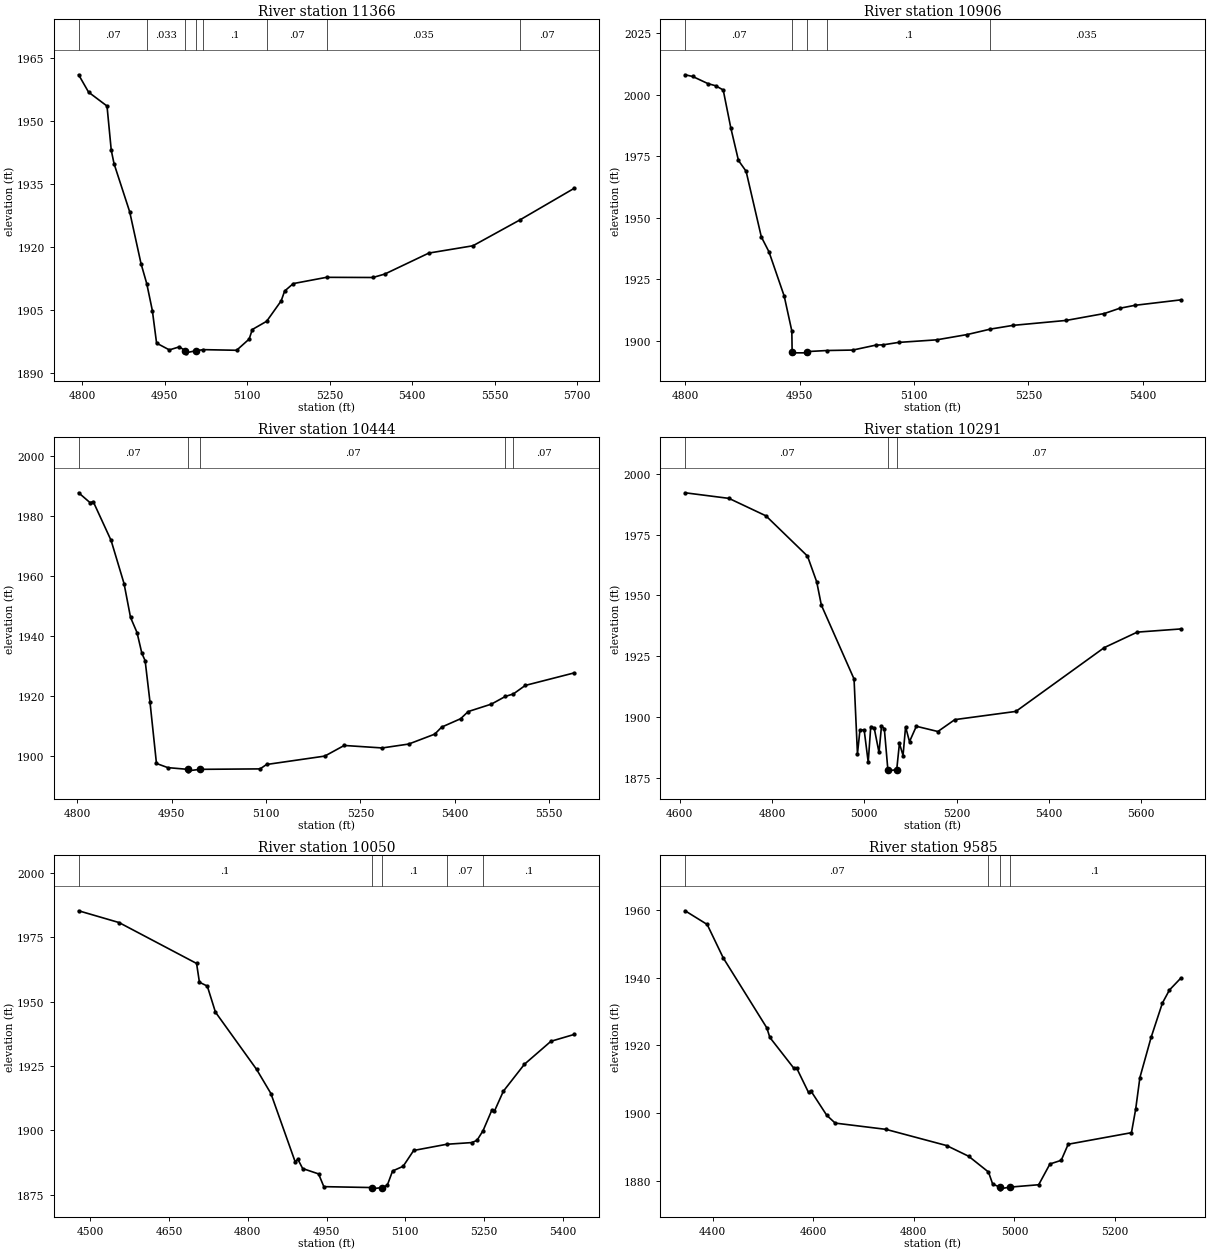
Type RM Length L Ch R = 1,11366,460,460,460
BEGIN DESCRIPTION:
Cypress Creek 2 23.0
END DESCRIPTION:
XS GIS Cut Line= 3
      1851974.99     13908275.00      1852175.00     13908325.00
      1852775.01     13908675.00
#Sta/Elev= 30
  4793.8 1961.01  4811.9 1956.87  4845.4 1953.57  4853.1 1943.05  4858.2 1939.84
  4886.6 1928.41  4907.2 1916.08  4917.6 1911.32  4927.8 1904.91  4935.5 1897.15
  4958.7 1895.54  4976.8 1896.26  4987.8 1895.34  4988.3 1894.84  5007.0 1895.34
  5020.4 1895.60  5081.0 1895.45  5103.8 1898.12  5109.5 1900.39  5135.6 1902.35
  5162.0 1907.21  5168.3 1909.55  5184.0 1911.32  5244.4 1912.81  5328.7 1912.77
  5350.2 1913.58  5430.4 1918.58  5510.6 1920.32  5595.7 1926.45  5694.6 1933.99
#Mann=8,-1,0
  4793.8    0.07       0  4917.6   0.033       0  4987.8   0.033       0
  5007.0   0.033       0  5020.4     0.1       0  5135.6    0.07       0
  5244.4   0.035       0  5595.7    0.07       0
Bank Sta=4987.8,5007
Exp/Cntr=0.3,0.1

Type RM Length L Ch R = 1,10906,462,462,462
BEGIN DESCRIPTION:
Cypress Creek 2 22.0
END DESCRIPTION:
XS GIS Cut Line= 3
      1851825.00     13908675.00      1852025.00     13908675.00
      1852475.00     13908675.00
#Sta/Elev= 30
  4799.7 2008.15  4809.7 2007.45  4829.7 2004.55  4839.7 2003.69  4849.7 2001.97
  4859.7 1986.48  4869.7 1973.29  4879.7 1968.92  4899.7 1942.20  4909.7 1936.15
  4929.7 1918.12  4939.7 1903.93  4940.1 1895.54  4940.6 1895.04  4958.8 1895.04
  4959.3 1895.54  4986.1 1895.99  5019.7 1896.17  5049.7 1898.17  5059.7 1898.31
  5079.7 1899.28  5129.7 1900.33  5169.7 1902.48  5200.2 1904.70  5229.7 1906.21
  5299.7 1908.23  5349.7 1911.04  5369.7 1913.16  5389.7 1914.37  5449.7 1916.58
#Mann=5,-1,0
  4799.7    0.07       0  4940.1    0.05       0  4959.3    0.07       0
  4986.1     0.1       0  5200.2   0.035       0
Bank Sta=4940.1,4959.3
Exp/Cntr=0.3,0.1

Type RM Length L Ch R = 1,10444,153,153,153
BEGIN DESCRIPTION:
Cypress Creek 2 21.0
END DESCRIPTION:
XS GIS Cut Line= 3
      1851974.95     13909075.01      1852175.00     13909025.00
      1852740.54     13908890.13
#Sta/Elev= 30
  4802.2 1987.72  4820.3 1984.44  4825.4 1984.77  4853.8 1971.81  4874.4 1957.40
  4884.7 1946.11  4895.0 1941.07  4902.7 1934.14  4907.9 1931.68  4915.6 1917.91
  4925.9 1897.37  4944.0 1895.98  4975.6 1895.41  4976.1 1894.91  4994.8 1895.41
  5090.6 1895.56  5100.9 1897.03  5193.4 1899.83  5224.3 1903.38  5284.7 1902.55
  5326.8 1903.85  5368.2 1907.16  5379.2 1909.51  5409.3 1912.30  5421.3 1914.69
  5458.3 1917.19  5480.6 1919.76  5493.2 1920.58  5512.1 1923.42  5589.8 1927.60
#Mann=5,-1,0
  4802.2    0.07       0  4975.6    0.05       0  4994.8    0.07       0
  5480.6     0.1       0  5493.2    0.07       0
Bank Sta=4975.6,4994.8
Exp/Cntr=0.3,0.1

Type RM Length L Ch R = 1,10291,241,241,241
BEGIN DESCRIPTION:
Cypress Creek 2 21.1
END DESCRIPTION:
XS GIS Cut Line= 4
      1851790.02     13909150.34      1852145.93     13909167.70
      1852390.72     13909060.06      1852838.63     13909013.19
#Sta/Elev= 30
  4611.5 1992.14  4706.6 1989.84  4786.7 1982.68  4876.8 1966.15  4896.8 1955.56
  4906.8 1946.06  4977.7 1915.71  4985.1 1885.02  4990.5 1894.74  4999.6 1894.84
  5008.4 1881.56  5013.9 1896.19  5021.4 1895.58  5031.8 1885.55  5037.2 1896.38
  5043.3 1895.34  5051.0 1878.52  5051.5 1878.02  5070.2 1878.52  5076.1 1889.31
  5083.9 1884.30  5089.4 1896.09  5097.9 1890.00  5112.7 1896.31  5159.4 1894.16
  5196.2 1899.04  5328.5 1902.41  5520.1 1928.60  5591.5 1934.95  5685.6 1936.25
#Mann=3,-1,0
  4611.5    0.07       0  5051.0    0.05       0  5070.2    0.07       0
Bank Sta=5051,5070.2
Exp/Cntr=0.3,0.1

Type RM Length L Ch R = 1,10050,465,465,465
BEGIN DESCRIPTION:
Cypress Creek 2 20.0
END DESCRIPTION:
XS GIS Cut Line= 4
      1851811.41     13909214.73      1852030.24     13909285.96
      1852325.00     13909325.00      1852739.24     13909364.66
#Sta/Elev= 30
  4477.9 1985.23  4554.8 1980.66  4702.5 1964.78  4707.9 1957.49  4722.9 1955.99
  4738.4 1945.88  4816.9 1923.60  4844.0 1914.28  4890.2 1887.77  4895.3 1888.76
  4904.5 1885.14  4934.8 1883.06  4944.8 1878.11  5036.0 1877.76  5036.5 1877.26
  5055.2 1877.76  5065.6 1878.63  5075.7 1884.19  5095.8 1886.01  5115.9 1892.16
  5178.9 1894.57  5226.4 1895.22  5236.4 1896.07  5247.9 1899.81  5264.6 1907.75
  5269.6 1907.39  5286.7 1915.18  5326.8 1925.64  5377.3 1934.56  5421.5 1937.21
#Mann=5,-1,0
  4477.9     0.1       0  5036.0    0.05       0  5055.2     0.1       0
  5178.9    0.07       0  5247.9     0.1       0
Bank Sta=5036,5055.2
Exp/Cntr=0.3,0.1

Type RM Length L Ch R = 1,9585,450,450,450
BEGIN DESCRIPTION:
Cypress Creek 2 19.0
END DESCRIPTION:
XS GIS Cut Line= 3
      1851824.97     13909975.01      1852425.00     13909725.00
      1852724.97     13909575.02
#Sta/Elev= 30
  4345.2 1959.71  4389.1 1955.67  4421.1 1945.78  4507.7 1925.14  4513.7 1922.32
  4561.4 1913.23  4566.8 1913.34  4590.6 1906.08  4596.0 1906.37  4626.9 1899.32
  4643.7 1897.02  4744.4 1895.18  4865.2 1890.39  4909.1 1887.23  4948.5 1882.57
  4956.8 1879.03  4970.9 1878.11  4971.4 1877.61  4990.4 1878.11  5048.3 1878.82
  5070.7 1884.95  5093.1 1886.03  5107.0 1890.78  5232.8 1894.19  5241.2 1901.14
  5249.6 1910.48  5271.9 1922.34  5294.3 1932.45  5308.3 1936.31  5330.6 1939.77
#Mann=4,-1,0
  4345.2    0.07       0  4948.5     0.1       0  4970.9    0.05       0
  4990.4     0.1       0
Bank Sta=4970.9,4990.4
Exp/Cntr=0.3,0.1

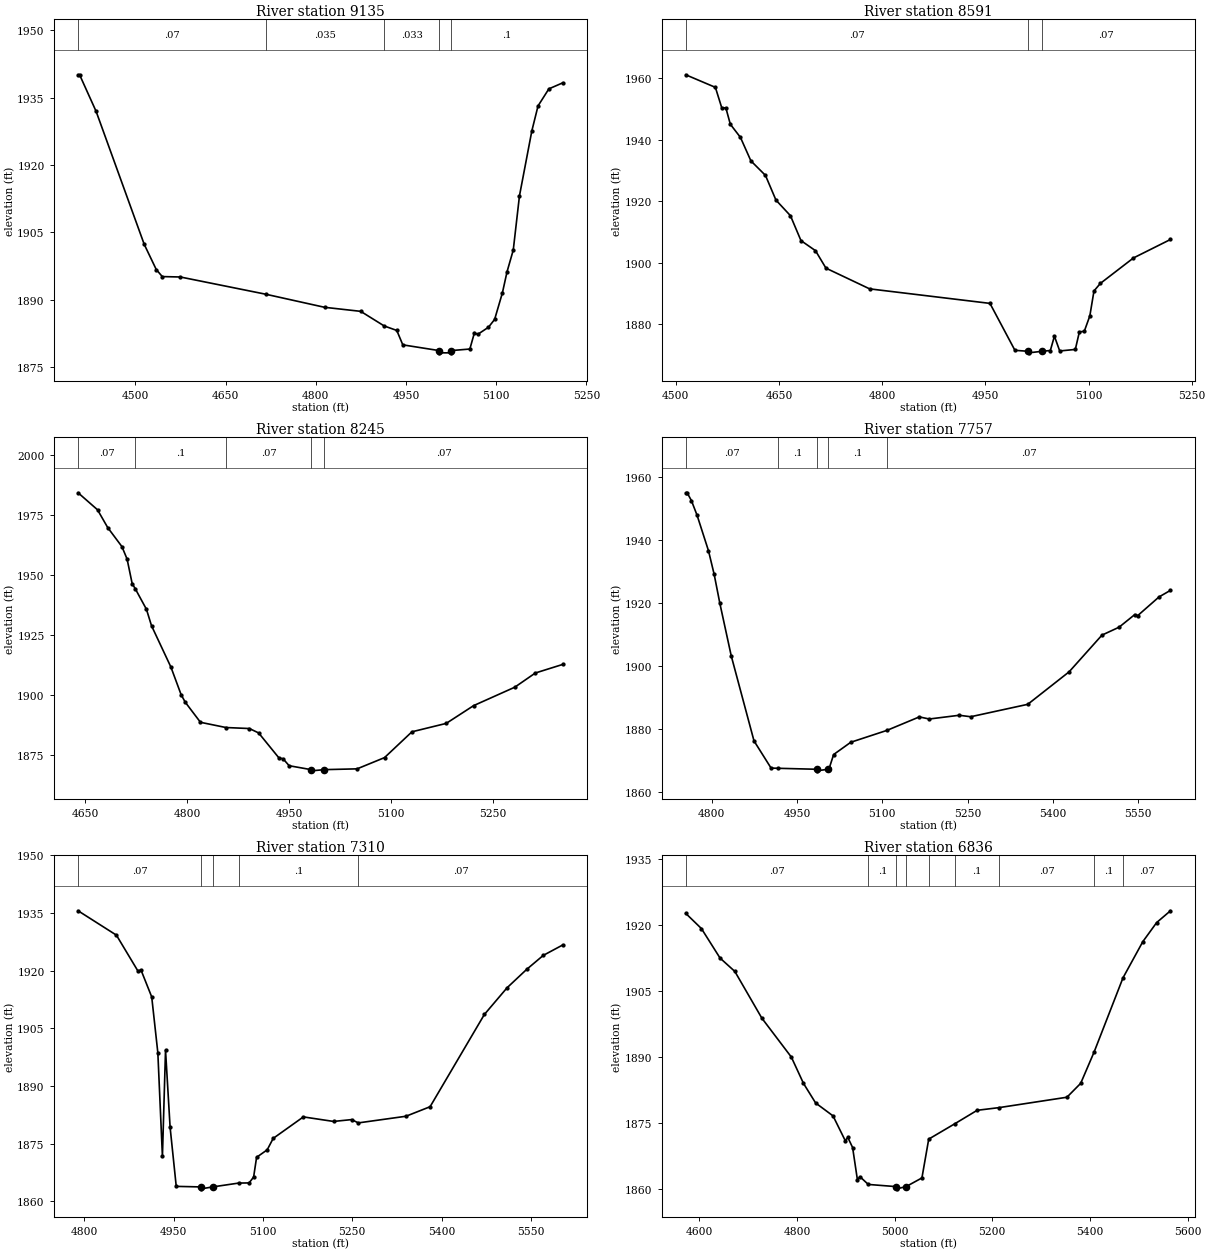
Type RM Length L Ch R = 1,9135,544,544,544
BEGIN DESCRIPTION:
Cypress Creek 2 18.0
END DESCRIPTION:
XS GIS Cut Line= 3
      1851925.03     13910075.00      1852525.00     13910075.00
      1852724.98     13910124.99
#Sta/Elev= 30
  4404.6 1940.12  4407.1 1940.12  4434.6 1931.95  4514.6 1902.31  4534.6 1896.70
  4544.6 1895.13  4574.6 1895.04  4716.6 1891.20  4814.6 1888.28  4874.6 1887.38
  4913.7 1884.12  4934.6 1883.12  4944.6 1879.91  5005.1 1878.63  5005.6 1878.13
  5024.2 1878.13  5024.7 1878.63  5056.1 1878.98  5063.8 1882.65  5069.0 1882.23
  5087.0 1883.83  5097.3 1885.58  5110.2 1891.49  5118.0 1896.23  5128.3 1901.05
  5138.6 1913.13  5159.2 1927.62  5169.5 1933.18  5187.5 1936.98  5210.7 1938.33
#Mann=5,-1,0
  4404.6    0.07       0  4716.6   0.035       0  4913.7   0.033       0
  5005.1   0.033       0  5024.7     0.1       0
Bank Sta=5005.1,5024.7
Exp/Cntr=0.3,0.1

Type RM Length L Ch R = 1,8591,346,346,346
BEGIN DESCRIPTION:
Cypress Creek 2 17.0
END DESCRIPTION:
XS GIS Cut Line= 3
      1851860.37     13910118.94      1852224.92     13910351.56
      1852372.26     13910580.37
#Sta/Elev= 30
  4514.5 1961.16  4557.6 1957.06  4566.9 1950.36  4572.8 1950.39  4579.3 1945.05
  4594.0 1940.77  4609.2 1933.12  4630.4 1928.38  4645.6 1920.35  4666.7 1915.25
  4682.0 1907.14  4703.1 1903.86  4718.3 1898.17  4781.8 1891.42  4956.7 1886.69
  4993.0 1871.40  5012.6 1871.08  5013.1 1870.58  5032.2 1871.08  5044.5 1871.34
  5050.4 1876.01  5058.1 1871.19  5080.8 1871.69  5086.7 1877.42  5093.8 1877.58
  5101.9 1882.63  5107.9 1890.73  5117.1 1893.18  5165.3 1901.49  5219.1 1907.51
#Mann=3,-1,0
  4514.5    0.07       0  5012.6    0.05       0  5032.2    0.07       0
Bank Sta=5012.6,5032.2
Exp/Cntr=0.3,0.1

Type RM Length L Ch R = 1,8245,488,488,488
BEGIN DESCRIPTION:
Cypress Creek 2 16.0
END DESCRIPTION:
XS GIS Cut Line= 3
      1851774.96     13910474.97      1852075.00     13910675.00
      1852425.04     13910624.99
#Sta/Elev= 30
  4639.4 1984.34  4668.0 1977.26  4683.0 1969.86  4704.0 1961.90  4711.6 1956.71
  4719.1 1946.47  4723.5 1944.42  4740.1 1935.79  4747.6 1928.92  4776.2 1911.68
  4791.2 1900.21  4797.2 1897.10  4819.7 1888.69  4857.3 1886.51  4891.8 1886.09
  4905.4 1884.26  4935.4 1873.82  4941.4 1873.49  4950.4 1870.59  4982.7 1868.96
  4983.2 1868.46  5002.3 1868.96  5050.5 1869.29  5090.9 1873.97  5131.3 1884.73
  5181.8 1888.23  5222.2 1895.64  5282.8 1903.31  5313.1 1909.23  5353.6 1912.82
#Mann=5,-1,0
  4639.4    0.07       0  4723.5     0.1       0  4857.3    0.07       0
  4982.7    0.05       0  5002.3    0.07       0
Bank Sta=4982.7,5002.3
Exp/Cntr=0.3,0.1

Type RM Length L Ch R = 1,7757,447,447,447
BEGIN DESCRIPTION:
Cypress Creek 2 15.0
END DESCRIPTION:
XS GIS Cut Line= 3
      1851725.00     13911125.00      1851975.00     13911125.00
      1852575.02     13911075.00
#Sta/Elev= 30
  4754.6 1955.09  4757.1 1955.09  4764.6 1952.59  4774.6 1947.90  4794.6 1936.63
  4804.6 1929.11  4814.6 1919.88  4834.6 1903.19  4874.6 1876.15  4904.6 1867.51
  4916.9 1867.44  4984.7 1867.13  4985.2 1866.63  5004.4 1867.13  5007.1 1867.63
  5014.6 1871.82  5044.7 1875.72  5108.3 1879.50  5165.2 1883.79  5182.7 1883.12
  5235.4 1884.31  5255.5 1883.84  5355.8 1887.79  5428.6 1898.14  5486.3 1909.81
  5516.4 1912.33  5544.0 1916.35  5549.0 1915.99  5586.6 1921.96  5606.7 1924.05
#Mann=5,-1,0
  4754.6    0.07       0  4916.9     0.1       0  4984.7    0.05       0
  5004.4     0.1       0  5108.3    0.07       0
Bank Sta=4984.7,5004.4
Exp/Cntr=0.3,0.1

Type RM Length L Ch R = 1,7310,474,474,474
BEGIN DESCRIPTION:
Cypress Creek 2 14.0
END DESCRIPTION:
XS GIS Cut Line= 3
      1851824.99     13911475.00      1852025.00     13911525.00
      1852624.96     13911425.01
#Sta/Elev= 30
  4789.4 1935.57  4853.8 1929.23  4889.9 1919.91  4895.1 1920.16  4913.1 1913.17
  4923.4 1898.63  4931.1 1871.67  4936.3 1899.31  4944.0 1879.25  4954.3 1863.89
  4995.8 1863.75  4996.3 1863.25  5015.5 1863.75  5059.2 1864.75  5076.7 1864.79
  5084.3 1866.31  5089.3 1871.45  5107.1 1873.39  5117.2 1876.37  5167.9 1881.96
  5218.6 1880.78  5249.0 1881.26  5260.2 1880.40  5340.3 1882.13  5380.8 1884.61
  5472.0 1908.60  5510.1 1915.54  5543.0 1920.32  5570.9 1923.96  5603.8 1926.69
#Mann=5,-1,0
  4789.4    0.07       0  4995.8    0.05       0  5015.5    0.07       0
  5059.2     0.1       0  5260.2    0.07       0
Bank Sta=4995.8,5015.5
Exp/Cntr=0.3,0.1

Type RM Length L Ch R = 1,6836,455,455,455
BEGIN DESCRIPTION:
Cypress Creek 2 13.0
END DESCRIPTION:
XS GIS Cut Line= 3
      1851824.99     13911775.00      1852225.00     13911925.00
      1852625.00     13911525.00
#Sta/Elev= 30
  4572.1 1922.65  4604.2 1919.20  4642.4 1912.49  4672.7 1909.45  4727.9 1898.85
  4788.4 1889.99  4813.3 1884.00  4838.2 1879.55  4873.8 1876.62  4898.7 1871.02
  4904.1 1871.71  4913.9 1869.43  4923.7 1862.13  4929.0 1862.80  4946.0 1861.04
  5003.6 1860.54  5004.1 1860.04  5023.3 1860.54  5055.9 1862.52  5069.8 1871.34
  5123.5 1874.85  5169.0 1877.89  5213.9 1878.50  5352.9 1880.86  5381.1 1884.02
  5408.5 1891.11  5467.8 1908.01  5508.4 1916.23  5536.7 1920.56  5565.0 1923.24
#Mann=9,-1,0
  4572.1    0.07       0  4946.0     0.1       0  5003.6    0.05       0
  5023.3     0.1       0  5069.8   0.033       0  5123.5     0.1       0
  5213.9    0.07       0  5408.5     0.1       0  5467.8    0.07       0
Bank Sta=5003.6,5023.3
Exp/Cntr=0.3,0.1

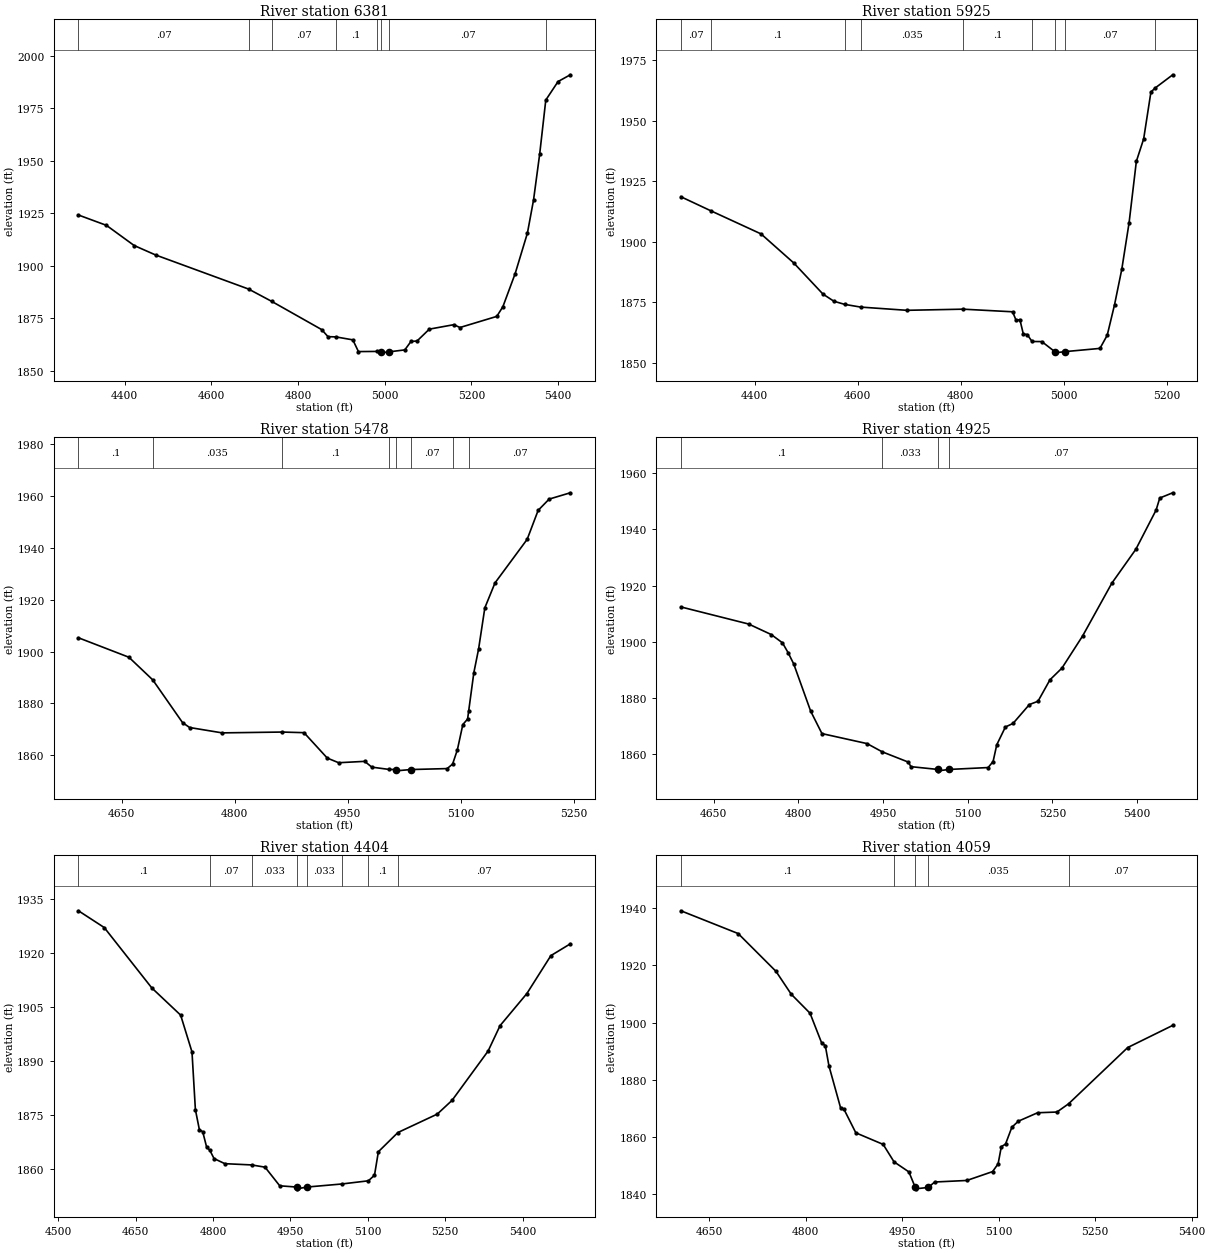
Type RM Length L Ch R = 1,6381,456,456,456
BEGIN DESCRIPTION:
Cypress Creek 2 12.0
END DESCRIPTION:
XS GIS Cut Line= 3
      1851725.01     13911875.01      1852275.00     13912325.00
      1852575.01     13912625.01
#Sta/Elev= 30
  4293.4 1924.15  4358.0 1919.22  4421.9 1909.61  4471.4 1905.10  4686.0 1888.84
  4739.3 1882.97  4854.7 1869.50  4869.1 1866.15  4887.4 1866.03  4926.5 1864.62
  4939.4 1859.03  4981.5 1859.10  4990.8 1858.93  4991.3 1858.43  5010.7 1858.93
  5046.4 1859.83  5060.6 1863.85  5074.7 1864.08  5103.0 1869.73  5159.6 1871.86
  5173.7 1870.51  5258.6 1875.81  5272.7 1880.42  5301.0 1896.19  5329.3 1915.52
  5343.4 1931.26  5357.6 1953.19  5371.7 1978.97  5400.0 1987.79  5428.3 1991.02
#Mann=8,-1,0
  4293.4    0.07       0  4686.0   0.035       0  4739.3    0.07       0
  4887.4     0.1       0  4981.5    0.07       0  4990.8    0.05       0
  5010.7    0.07       0  5371.7    0.07       0
Bank Sta=4990.8,5010.7
Exp/Cntr=0.3,0.1

Type RM Length L Ch R = 1,5925,447,447,447
BEGIN DESCRIPTION:
Cypress Creek 2 11.0
END DESCRIPTION:
XS GIS Cut Line= 3
      1851525.01     13912175.01      1852075.00     13912675.00
      1852224.98     13912824.98
#Sta/Elev= 30
  4256.7 1918.58  4314.8 1912.79  4412.4 1903.25  4476.0 1891.26  4532.7 1878.43
  4554.0 1875.47  4574.8 1874.19  4605.9 1873.07  4695.6 1871.74  4804.9 1872.21
  4901.0 1871.13  4907.8 1867.64  4915.2 1867.90  4921.9 1861.93  4929.4 1861.75
  4938.8 1858.88  4957.8 1858.84  4982.9 1854.70  4983.4 1854.20  5002.8 1854.70
  5070.7 1856.03  5084.8 1861.44  5099.0 1874.00  5113.1 1888.65  5127.3 1907.86
  5141.4 1933.17  5155.6 1942.43  5169.7 1961.76  5177.8 1963.40  5212.1 1968.88
#Mann=9,-1,0
  4256.7    0.07       0  4314.8     0.1       0  4574.8    0.07       0
  4605.9   0.035       0  4804.9     0.1       0  4938.8    0.07       0
  4982.9    0.05       0  5002.8    0.07       0  5177.8     0.1       0
Bank Sta=4982.9,5002.8
Exp/Cntr=0.3,0.1

Type RM Length L Ch R = 1,5478,553,553,553
BEGIN DESCRIPTION:
Cypress Creek 2 10.0
END DESCRIPTION:
XS GIS Cut Line= 3
      1851474.99     13912374.98      1851675.00     13912725.00
      1851824.98     13912924.97
#Sta/Elev= 30
  4592.4 1905.33  4659.4 1897.82  4691.1 1889.07  4730.6 1872.60  4740.0 1870.70
  4783.2 1868.63  4862.7 1868.95  4891.9 1868.71  4922.8 1858.90  4937.9 1857.11
  4972.5 1857.64  4981.9 1855.41  5004.7 1854.53  5013.7 1854.48  5014.2 1853.98
  5033.7 1854.48  5082.0 1854.85  5089.2 1856.60  5095.5 1862.06  5102.8 1871.85
  5109.1 1873.96  5110.5 1876.98  5117.4 1891.86  5123.7 1900.98  5132.0 1916.89
  5145.5 1926.51  5188.2 1943.32  5202.8 1954.52  5217.4 1958.85  5245.5 1961.29
#Mann=8,-1,0
  4592.4     0.1       0  4691.1   0.035       0  4862.7     0.1       0
  5004.7    0.07       0  5013.7    0.05       0  5033.7    0.07       0
  5089.2     0.1       0  5110.5    0.07       0
Bank Sta=5013.7,5033.7
Exp/Cntr=0.3,0.1

Type RM Length L Ch R = 1,4925,521,521,521
BEGIN DESCRIPTION:
Cypress Creek 2 9.0
END DESCRIPTION:
XS GIS Cut Line= 3
      1851175.00     13912325.00      1851175.00     13912725.00
      1851425.00     13913125.00
#Sta/Elev= 30
  4591.7 1912.38  4711.7 1906.29  4751.7 1902.55  4771.7 1899.59  4781.7 1896.09
  4791.7 1892.04  4821.7 1875.23  4841.7 1867.22  4921.7 1863.65  4948.5 1860.72
  4994.7 1857.06  4999.4 1855.43  5047.2 1854.44  5047.7 1853.94  5067.2 1854.44
  5136.2 1855.11  5145.0 1857.25  5151.5 1863.22  5166.8 1869.57  5180.4 1870.85
  5209.3 1877.57  5224.6 1878.75  5245.8 1886.40  5267.1 1890.59  5303.6 1902.01
  5355.5 1920.86  5398.0 1932.93  5433.9 1946.92  5440.4 1951.21  5463.4 1953.08
#Mann=4,-1,0
  4591.7     0.1       0  4948.5   0.033       0  5047.2   0.033       0
  5067.2    0.07       0
Bank Sta=5047.2,5067.2
Exp/Cntr=0.3,0.1

Type RM Length L Ch R = 1,4404,345,345,345
BEGIN DESCRIPTION:
Cypress Creek 2 8.0
END DESCRIPTION:
XS GIS Cut Line= 3
      1850424.98     13912374.97      1850725.00     13912725.00
      1850925.02     13913175.04
#Sta/Elev= 30
  4539.0 1931.63  4589.0 1926.98  4681.2 1910.23  4737.1 1902.69  4759.1 1892.48
  4765.7 1876.47  4773.4 1870.94  4779.9 1870.35  4787.6 1866.02  4793.5 1865.25
  4801.9 1862.90  4822.8 1861.49  4874.8 1861.14  4900.7 1860.52  4929.2 1855.35
  4961.9 1855.01  4962.4 1854.51  4982.2 1855.01  5049.1 1855.85  5101.1 1856.74
  5112.9 1858.29  5120.4 1864.80  5158.3 1870.13  5234.6 1875.24  5263.3 1879.06
  5333.1 1892.72  5356.3 1899.77  5408.3 1908.68  5454.8 1919.19  5492.5 1922.46
#Mann=8,-1,0
  4539.0     0.1       0  4793.5    0.07       0  4874.8   0.033       0
  4961.9   0.033       0  4982.2   0.033       0  5049.1    0.07       0
  5101.1     0.1       0  5158.3    0.07       0
Bank Sta=4961.9,4982.2
Exp/Cntr=0.3,0.1

Type RM Length L Ch R = 1,4059,222,222,222
BEGIN DESCRIPTION:
Cypress Creek 2 7.1
END DESCRIPTION:
XS GIS Cut Line= 4
      1850332.91     13912352.87      1850443.58     13912615.45
      1850450.09     13912830.29      1850456.60     13913095.02
#Sta/Elev= 30
  4605.8 1939.08  4694.9 1931.11  4753.7 1917.89  4777.4 1909.89  4806.6 1903.25
  4824.9 1892.72  4830.3 1891.96  4836.0 1884.83  4854.0 1870.25  4859.5 1869.59
  4877.8 1861.42  4920.3 1857.37  4937.2 1851.27  4960.3 1847.75  4970.2 1842.33
  4970.7 1841.83  4990.5 1842.33  5000.4 1844.22  5050.4 1844.76  5090.4 1847.86
  5099.0 1850.57  5104.0 1856.58  5110.5 1857.48  5120.4 1863.38  5130.4 1865.48
  5160.4 1868.44  5190.4 1868.69  5208.5 1871.56  5300.5 1891.25  5370.5 1899.00
#Mann=5,-1,0
  4605.8     0.1       0  4937.2   0.035       0  4970.2   0.035       0
  4990.5   0.035       0  5208.5    0.07       0
Bank Sta=4970.2,4990.5
Exp/Cntr=0.3,0.1

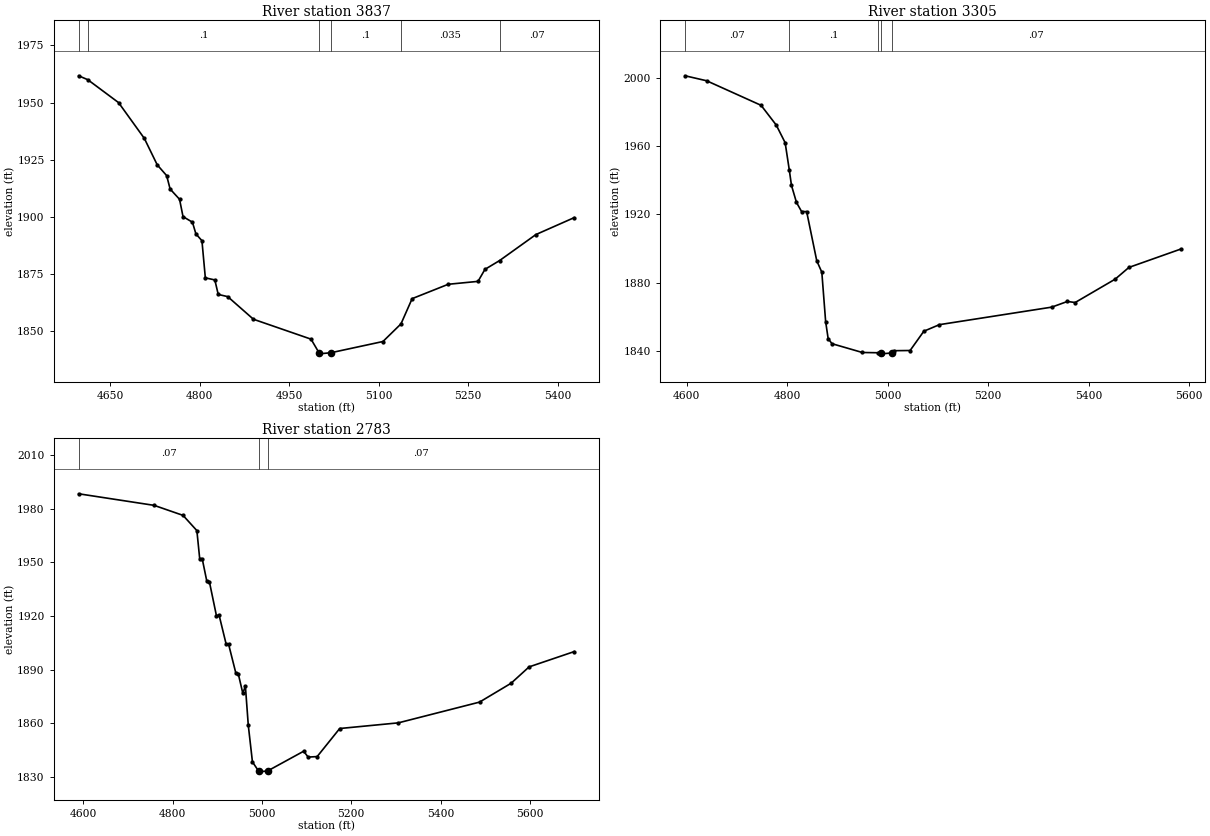
Type RM Length L Ch R = 1,3837,532,532,532
BEGIN DESCRIPTION:
Cypress Creek 2 7.0
END DESCRIPTION:
XS GIS Cut Line= 3
      1849875.03     13912525.02      1850225.00     13912725.00
      1850375.01     13913125.02
#Sta/Elev= 30
  4597.1 1961.74  4612.4 1960.03  4664.0 1950.01  4707.2 1934.36  4728.8 1922.80
  4744.6 1918.09  4750.4 1912.23  4766.2 1907.74  4772.0 1900.17  4787.8 1897.72
  4793.6 1892.62  4803.7 1889.64  4809.4 1873.40  4825.3 1872.49  4831.0 1866.15
  4846.9 1865.19  4890.0 1855.30  4986.5 1846.60  4999.8 1840.68  5000.3 1840.18
  5020.1 1840.68  5107.0 1845.57  5137.2 1853.27  5155.9 1864.31  5216.4 1870.59
  5266.3 1871.86  5277.9 1877.11  5302.4 1880.95  5363.3 1892.33  5427.4 1899.72
#Mann=6,-1,0
  4597.1    0.07       0  4612.4     0.1       0  4999.8    0.05       0
  5020.1     0.1       0  5137.2   0.035       0  5302.4    0.07       0
Bank Sta=4999.8,5020.1
Exp/Cntr=0.3,0.1

Type RM Length L Ch R = 1,3305,522,522,522
BEGIN DESCRIPTION:
Cypress Creek 2 6.0
END DESCRIPTION:
XS GIS Cut Line= 3
      1849374.98     13912875.00      1849775.00     13912925.00
      1850274.97     13913224.98
#Sta/Elev= 30
  4597.1 2001.05  4640.0 1998.13  4748.3 1983.78  4778.5 1972.24  4796.2 1961.93
  4804.4 1946.11  4808.8 1936.95  4818.8 1926.97  4828.9 1921.68  4839.0 1921.64
  4859.1 1892.91  4869.2 1886.20  4876.8 1857.31  4881.8 1847.38  4889.4 1844.40
  4949.8 1839.26  4980.8 1839.11  4987.6 1838.97  4988.1 1838.47  5007.9 1838.97
  5013.8 1840.31  5044.9 1840.42  5072.2 1851.69  5103.2 1855.53  5326.8 1865.78
  5357.9 1869.09  5373.4 1868.48  5453.1 1882.15  5480.3 1888.99  5583.3 1899.70
#Mann=5,-1,0
  4597.1    0.07       0  4804.4     0.1       0  4980.8    0.07       0
  4987.6    0.05       0  5007.9    0.07       0
Bank Sta=4987.6,5007.9
Exp/Cntr=0.3,0.1

Type RM Length L Ch R = 1,2783,517,517,517
BEGIN DESCRIPTION:
Cypress Creek 2 5.0
END DESCRIPTION:
XS GIS Cut Line= 3
      1849225.02     13913175.01      1849575.00     13913375.00
      1850275.01     13913275.00
#Sta/Elev= 30
  4589.1 1988.42  4758.2 1981.94  4823.0 1976.33  4854.0 1967.81  4860.5 1951.70
  4866.2 1951.78  4876.3 1939.46  4882.0 1939.23  4897.9 1920.08  4903.6 1920.67
  4919.5 1904.33  4925.2 1904.06  4941.1 1888.25  4946.8 1887.58  4956.9 1876.77
  4962.7 1880.75  4969.2 1858.81  4978.5 1838.32  4992.1 1833.26  4992.6 1832.76
  5012.5 1833.26  5093.2 1844.29  5103.3 1841.02  5123.5 1841.30  5174.0 1857.01
  5305.3 1860.18  5487.2 1871.79  5557.9 1882.34  5598.3 1891.51  5699.3 1900.07
#Mann=3,-1,0
  4589.1    0.07       0  4992.1    0.05       0  5012.5    0.07       0
Bank Sta=4992.1,5012.5
Exp/Cntr=0.3,0.1