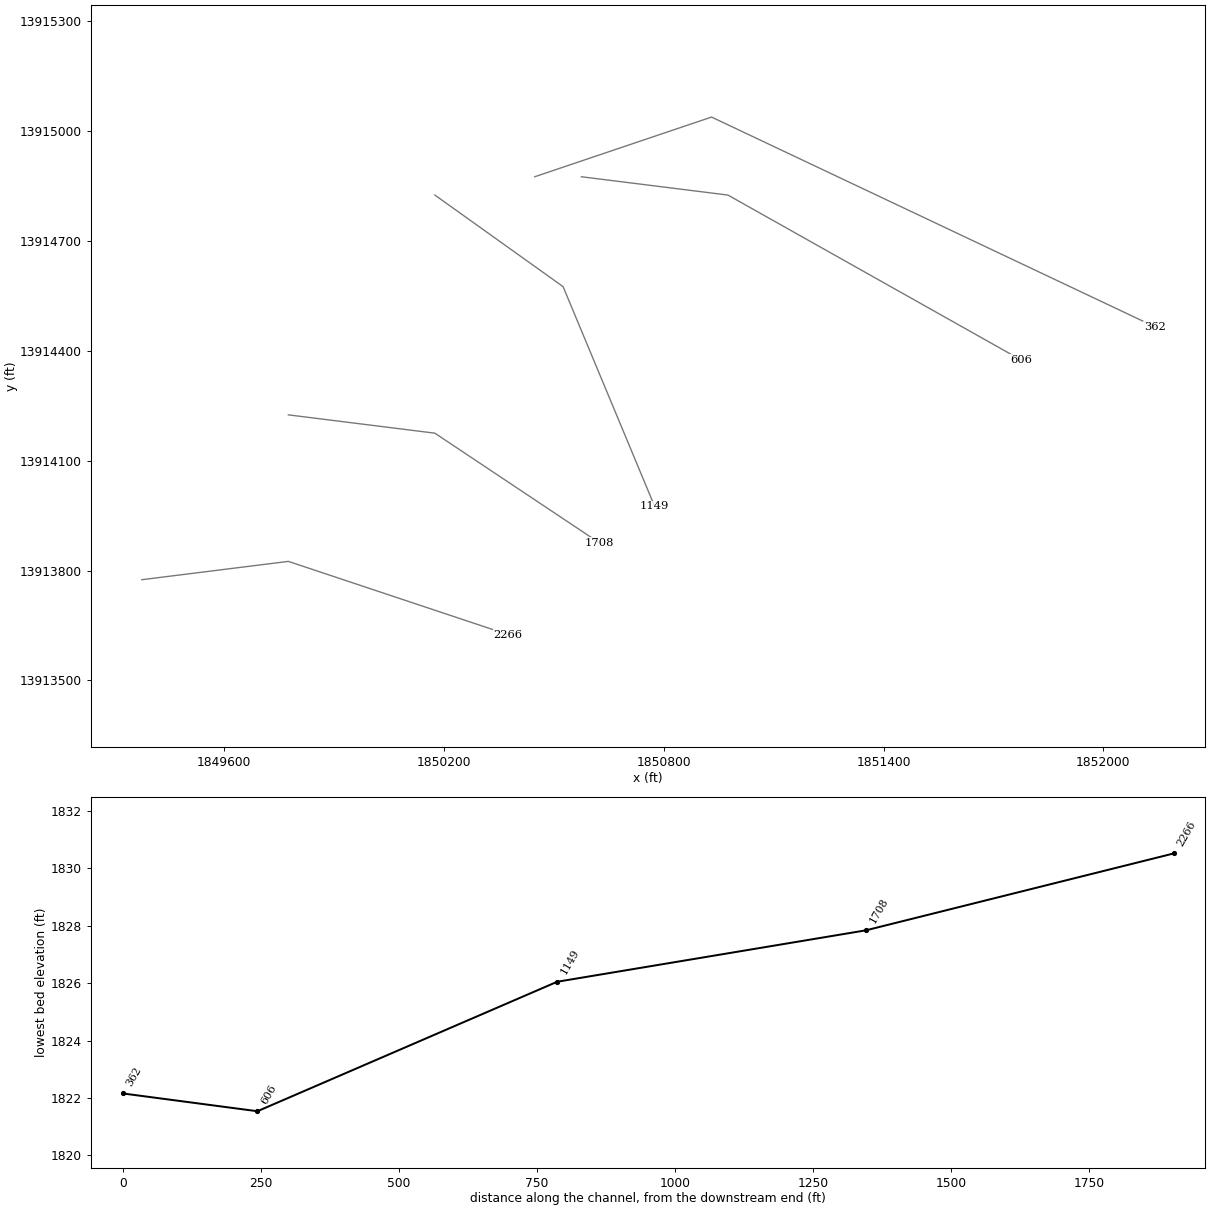
HEC-RAS study Cypress Creek 2.prj: Cypress Creek 2 Base Level Engineering

--- Cypress Creek 2.g01 (geometry) --- (continued)

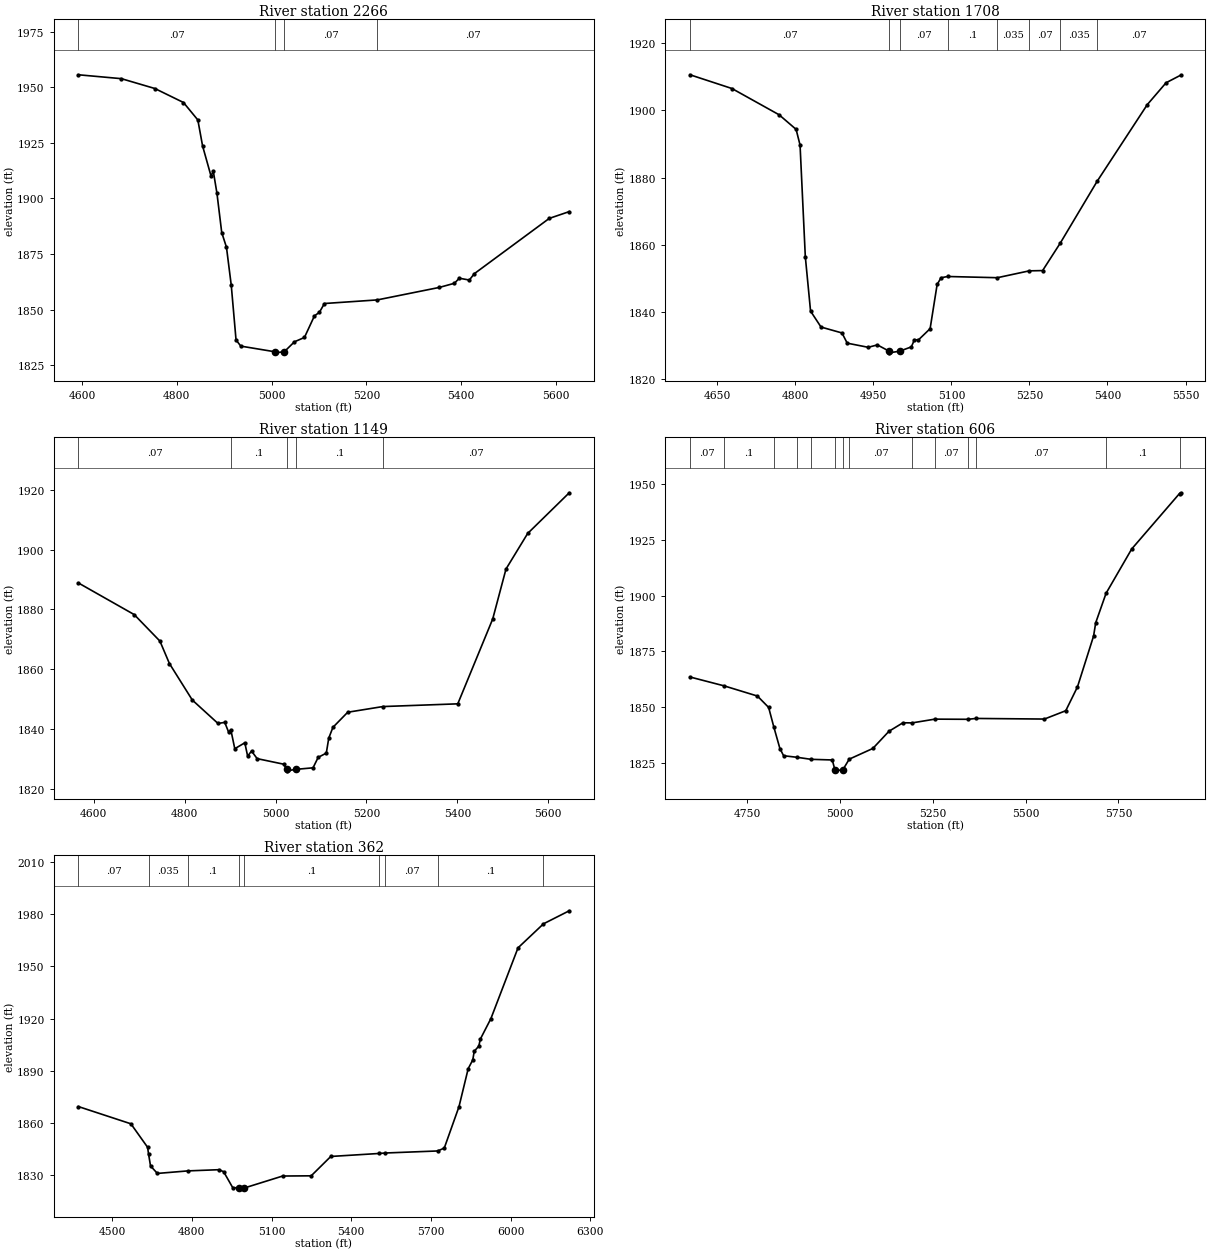
Type RM Length L Ch R = 1,2266,558,558,558
BEGIN DESCRIPTION:
Cypress Creek 2 4.0
END DESCRIPTION:
XS GIS Cut Line= 3
      1849374.98     13913775.00      1849775.00     13913825.00
      1850375.01     13913625.00
#Sta/Elev= 30
  4592.3 1955.66  4683.0 1953.91  4753.6 1949.48  4814.0 1943.18  4844.3 1935.33
  4854.3 1923.64  4872.0 1910.17  4877.0 1912.14  4884.6 1902.36  4894.7 1884.66
  4904.7 1878.04  4914.8 1860.93  4924.9 1836.30  4935.0 1833.54  5006.3 1831.02
  5006.8 1830.52  5026.7 1831.02  5048.1 1835.49  5069.2 1837.44  5090.3 1847.16
  5100.8 1848.77  5111.4 1852.72  5222.9 1854.34  5353.8 1859.96  5385.5 1861.82
  5396.0 1864.10  5417.1 1863.28  5427.6 1866.14  5585.7 1891.02  5627.9 1894.08
#Mann=4,-1,0
  4592.3    0.07       0  5006.3    0.05       0  5026.7    0.07       0
  5222.9    0.07       0
Bank Sta=5006.3,5026.7
Exp/Cntr=0.3,0.1

Type RM Length L Ch R = 1,1708,559,559,559
BEGIN DESCRIPTION:
Cypress Creek 2 3.0
END DESCRIPTION:
XS GIS Cut Line= 3
      1849775.03     13914225.00      1850175.00     13914175.00
      1850624.99     13913875.01
#Sta/Elev= 30
  4597.2 1910.63  4677.8 1906.54  4768.5 1898.72  4801.2 1894.38  4808.8 1889.71
  4818.9 1856.50  4829.0 1840.27  4849.1 1835.52  4889.4 1833.76  4899.5 1830.72
  4939.8 1829.49  4957.5 1830.20  4980.0 1828.34  4980.5 1827.84  5000.4 1828.34
  5022.8 1829.61  5028.8 1831.76  5036.3 1831.67  5058.9 1835.03  5072.4 1848.20
  5079.9 1850.19  5092.6 1850.57  5188.2 1850.21  5249.5 1852.25  5275.2 1852.33
  5309.3 1860.54  5380.1 1878.92  5476.5 1901.74  5512.6 1908.25  5541.1 1910.54
#Mann=8,-1,0
  4597.2    0.07       0  4980.0    0.05       0  5000.4    0.07       0
  5092.6     0.1       0  5188.2   0.035       0  5249.5    0.07       0
  5309.3   0.035       0  5380.1    0.07       0
Bank Sta=4980,5000.4
Exp/Cntr=0.3,0.1

Type RM Length L Ch R = 1,1149,543,543,543
BEGIN DESCRIPTION:
Cypress Creek 2 2.0
END DESCRIPTION:
XS GIS Cut Line= 3
      1850174.98     13914825.01      1850525.00     13914575.00
      1850774.98     13913975.04
#Sta/Elev= 30
  4566.1 1888.86  4689.0 1878.28  4745.5 1869.42  4766.4 1861.92  4816.8 1849.71
  4873.3 1841.89  4888.1 1842.25  4896.7 1838.98  4901.5 1839.81  4910.2 1833.45
  4932.3 1835.42  4938.5 1830.96  4947.1 1832.67  4959.4 1830.13  5017.9 1828.27
  5024.4 1826.55  5024.9 1826.05  5044.9 1826.55  5082.4 1827.06  5093.7 1830.55
  5111.6 1831.98  5117.0 1836.99  5126.2 1840.60  5158.7 1845.64  5236.0 1847.54
  5400.9 1848.45  5477.8 1876.83  5507.0 1893.52  5554.7 1905.41  5646.2 1919.01
#Mann=5,-1,0
  4566.1    0.07       0  4901.5     0.1       0  5024.4    0.05       0
  5044.9     0.1       0  5236.0    0.07       0
Bank Sta=5024.4,5044.9
Exp/Cntr=0.3,0.1

Type RM Length L Ch R = 1,606,244,244,244
BEGIN DESCRIPTION:
Cypress Creek 2 1.0
END DESCRIPTION:
XS GIS Cut Line= 3
      1850575.01     13914875.00      1850975.00     13914825.00
      1851775.02     13914374.99
#Sta/Elev= 30
  4596.9 1863.56  4688.7 1859.59  4778.3 1855.03  4808.5 1849.93  4822.5 1841.14
  4838.8 1831.53  4848.8 1828.30  4885.3 1827.60  4922.3 1826.70  4979.8 1826.41
  4986.7 1822.04  4987.2 1821.54  5008.3 1822.04  5025.4 1826.77  5088.9 1831.56
  5132.3 1839.25  5169.9 1843.06  5194.6 1843.01  5255.8 1844.69  5345.0 1844.62
  5366.1 1845.00  5550.7 1844.73  5608.1 1848.46  5639.6 1859.12  5683.0 1881.91
  5688.7 1887.85  5716.6 1901.05  5785.6 1920.89  5914.3 1945.72  5917.9 1946.05
#Mann=14,-1,0
  4596.9    0.07       0  4688.7     0.1       0  4822.5   0.035       0
  4885.3     0.1       0  4922.3   0.035       0  4986.7   0.035       0
  5008.3   0.035       0  5025.4    0.07       0  5194.6   0.035       0
  5255.8    0.07       0  5345.0   0.035       0  5366.1    0.07       0
  5716.6     0.1       0  5914.3    0.07       0
Bank Sta=4986.7,5008.3
Exp/Cntr=0.3,0.1

Type RM Length L Ch R = 1,362,0,0,0
BEGIN DESCRIPTION:
Cypress Creek 2 0.0
END DESCRIPTION:
XS GIS Cut Line= 3
      1850447.80     13914875.08      1850930.31     13915037.94
      1852140.20     13914465.57
#Sta/Elev= 30
  4372.9 1869.42  4570.5 1859.52  4633.5 1846.01  4636.8 1842.32  4644.4 1835.33
  4670.2 1831.01  4785.2 1832.47  4902.3 1833.16  4919.6 1831.99  4953.7 1822.87
  4976.1 1822.66  4976.6 1822.16  4997.7 1822.66  5141.8 1829.52  5249.2 1829.64
  5323.0 1840.76  5504.0 1842.47  5528.9 1842.75  5725.5 1843.92  5750.2 1845.60
  5805.5 1869.34  5840.2 1891.21  5857.4 1896.21  5862.9 1901.18  5880.2 1904.17
  5885.7 1908.11  5925.7 1919.97  6027.7 1960.59  6123.6 1974.40  6220.6 1981.89
#Mann=9,-1,0
  4372.9    0.07       0  4636.8   0.035       0  4785.2     0.1       0
  4976.1    0.05       0  4997.7     0.1       0  5504.0   0.035       0
  5528.9    0.07       0  5725.5     0.1       0  6123.6    0.07       0
Bank Sta=4976.1,4997.7
Exp/Cntr=0.3,0.1

Chan Stop Cuts=-1