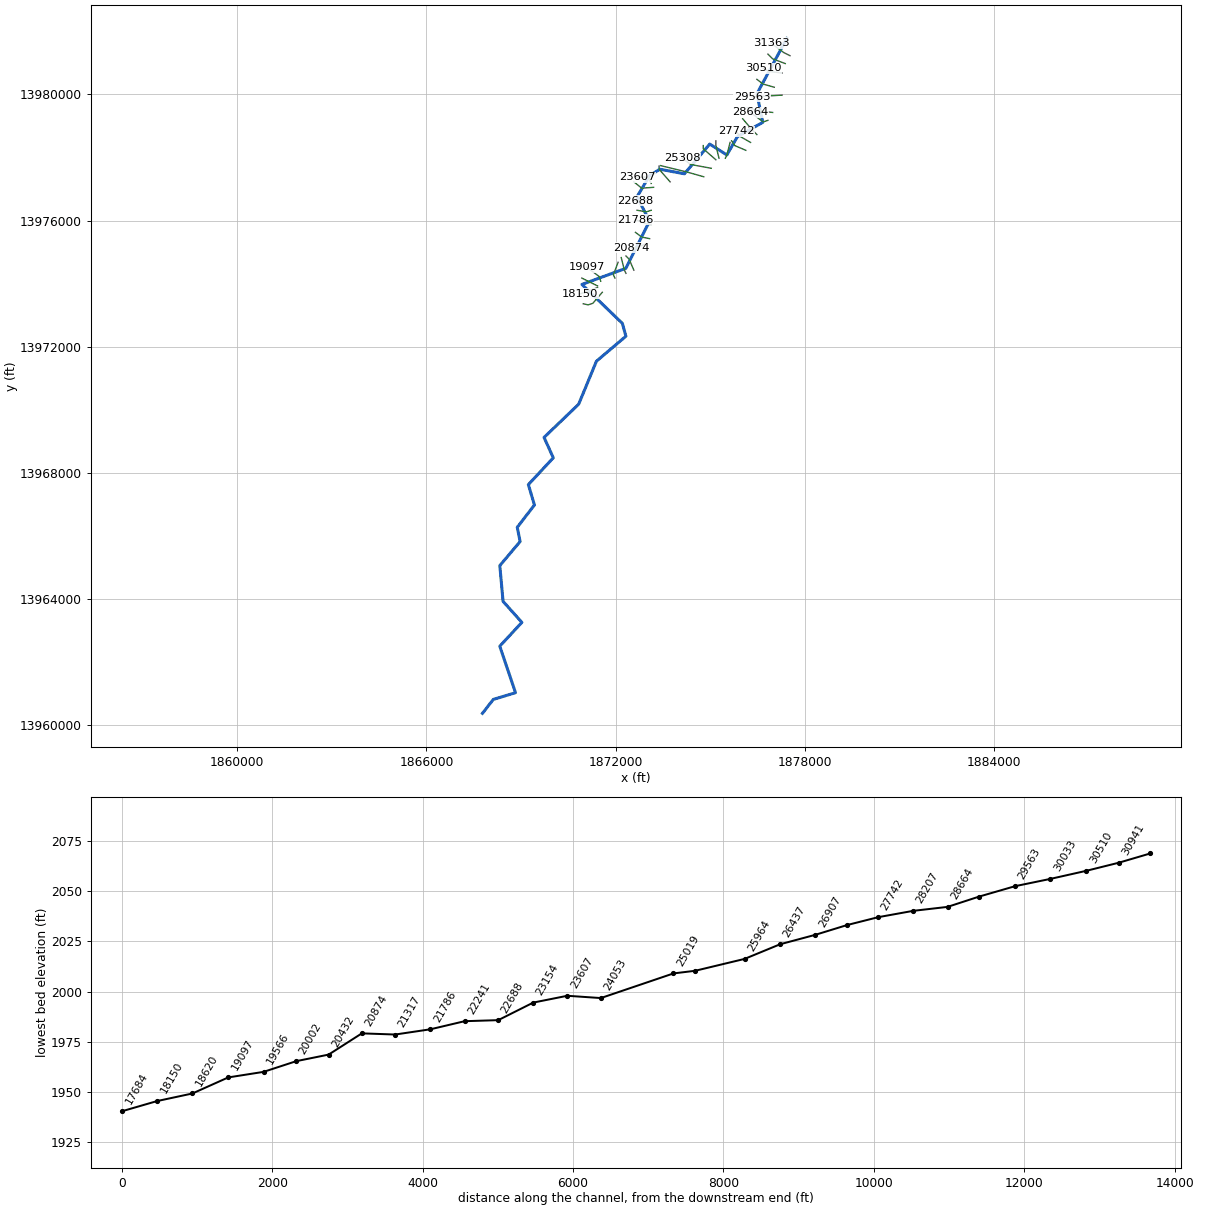
--- Dry Branch.prj (project) ---

Proj Title=Dry Branch Base Level Engineering
Current Plan=p01
Default Exp/Contr=0.3,0.1
English Units
Geom File=g01
Flow File=f01
Plan File=p01
Y Axis Title=Elevation
X Axis Title(PF)=Main Channel Distance
X Axis Title(XS)=Station
BEGIN DESCRIPTION:
Dry Branch
END DESCRIPTION:
DSS Export Rating Curves= 0
DSS Export Rating Curve Sorted= 0
DSS Export Volume Flow Curves= 0
DXF OffsetX= 0
DXF OffsetY= 0
DXF ScaleX= 1
DXF ScaleY= 10

--- Dry Branch.p01 (plan) ---

Plan Title=Multiple Run
Short Identifier=Multiple
Geom File=g01
Flow File=f01
Subcritical Flow
K Sum by GR= 0
Std Step Tol= 0.01
Critical Tol= 0.01
Num of Std Step Trials= 20
Max Error Tol= 0.3
Flow Tol Ratio= 0.001
Split Flow NTrial= 30
Split Flow Tol= 0.02
Split Flow Ratio= 0.02
Log Output Level= 0
Friction Slope Method= 1
Unsteady Friction Slope Method= 2
Unsteady Bridges Friction Slope Method= 1
Parabolic Critical Depth
Global Vel Dist=  1 , 1 , 1
Global Log Level= 0
CheckData=True
Encroach Param= -1, 0, 0, 0
BEGIN DESCRIPTION:
Multiple Run
END DESCRIPTION:

--- Dry Branch.f01 (steady flow) ---

Flow Title=Multiple
Number of Profiles=7
Profile Names=10-year,25-year,50-year,1pct_min,100-year,1pct_plu,500-year
River Rch & RM= Dry Branch,Reach-1,31363
    1745    3036    4285    2916    5818   11608   10606
River Rch & RM= Dry Branch,Reach-1,25308
    2287    4034    5746    3943    7868   15698   14591
River Rch & RM= Dry Branch,Reach-1,23607
    2828    5033    7211    4974    9924   19800   18593
River Rch & RM= Dry Branch,Reach-1,18620
    3082    5511    7922    5481   10935   21819   20615
River Rch & RM= Dry Branch,Reach-1,14033
    3378    6059    8728    6049   12069   24081   22832
River Rch & RM= Dry Branch,Reach-1,12457
    3427    6152    8867    6147   12266   24474   23225
River Rch & RM= Dry Branch,Reach-1,10604
    3601    6477    9347    6488   12945   25829   24569
River Rch & RM= Dry Branch,Reach-1,8785
    5683   10397   15179   10643   21236   42372   41134
River Rch & RM= Dry Branch,Reach-1,8269
    5855   10716   15646   10971   21889   43675   42397
River Rch & RM= Dry Branch,Reach-1,4590
    5984   10950   15987   11208   22363   44620   43296
River Rch & RM= Dry Branch,Reach-1,942
    6071   11114   16231   11381   22708   45309   43984
Boundary for River Rch & Prof#=Dry Branch,Reach-1,1
Up Type=0
Dn Type=3
Dn Slope=0.005
Boundary for River Rch & Prof#=Dry Branch,Reach-1,2
Up Type=0
Dn Type=3
Dn Slope=0.005
Boundary for River Rch & Prof#=Dry Branch,Reach-1,3
Up Type=0
Dn Type=3
Dn Slope=0.005
Boundary for River Rch & Prof#=Dry Branch,Reach-1,4
Up Type=0
Dn Type=3
Dn Slope=0.005
Boundary for River Rch & Prof#=Dry Branch,Reach-1,5
Up Type=0
Dn Type=3
Dn Slope=0.005
Boundary for River Rch & Prof#=Dry Branch,Reach-1,6
Up Type=0
Dn Type=3
Dn Slope=0.005
Boundary for River Rch & Prof#=Dry Branch,Reach-1,7
Up Type=0
Dn Type=3
Dn Slope=0.005

--- Dry Branch.g01 (geometry) ---

Geom Title=Existing Conditions
Program Version=4.10

River Reach=Dry Branch      ,Reach-1
Reach XY= 30
        1877425.       13981775.      1876477.24     13980019.07
       1876661.6      13979111.7      1875858.29     13978658.37
      1875523.35     13978078.11      1874980.89     13978423.03
      1874177.54      13977480.7      1873399.91     13977625.21
        1873075.       13977425.      1872674.58       13976750.
      1873072.74     13975980.94       1872321.2     13974483.64
      1870928.67     13973973.42      1872211.38     13972738.22
      1872323.03     13972330.89      1871388.47     13971538.57
        1870825.       13970175.      1869728.34     13969123.28
      1870021.47     13968476.46      1869230.41     13967627.42
      1869423.24     13966981.12      1868878.54     13966273.54
       1868969.6     13965822.57      1868325.38     13965059.84
      1868428.54     13963926.47      1869024.93     13963259.61
      1868325.06     13962504.97        1868823.     13961030.82
      1868118.83     13960817.14        1867775.       13960375.

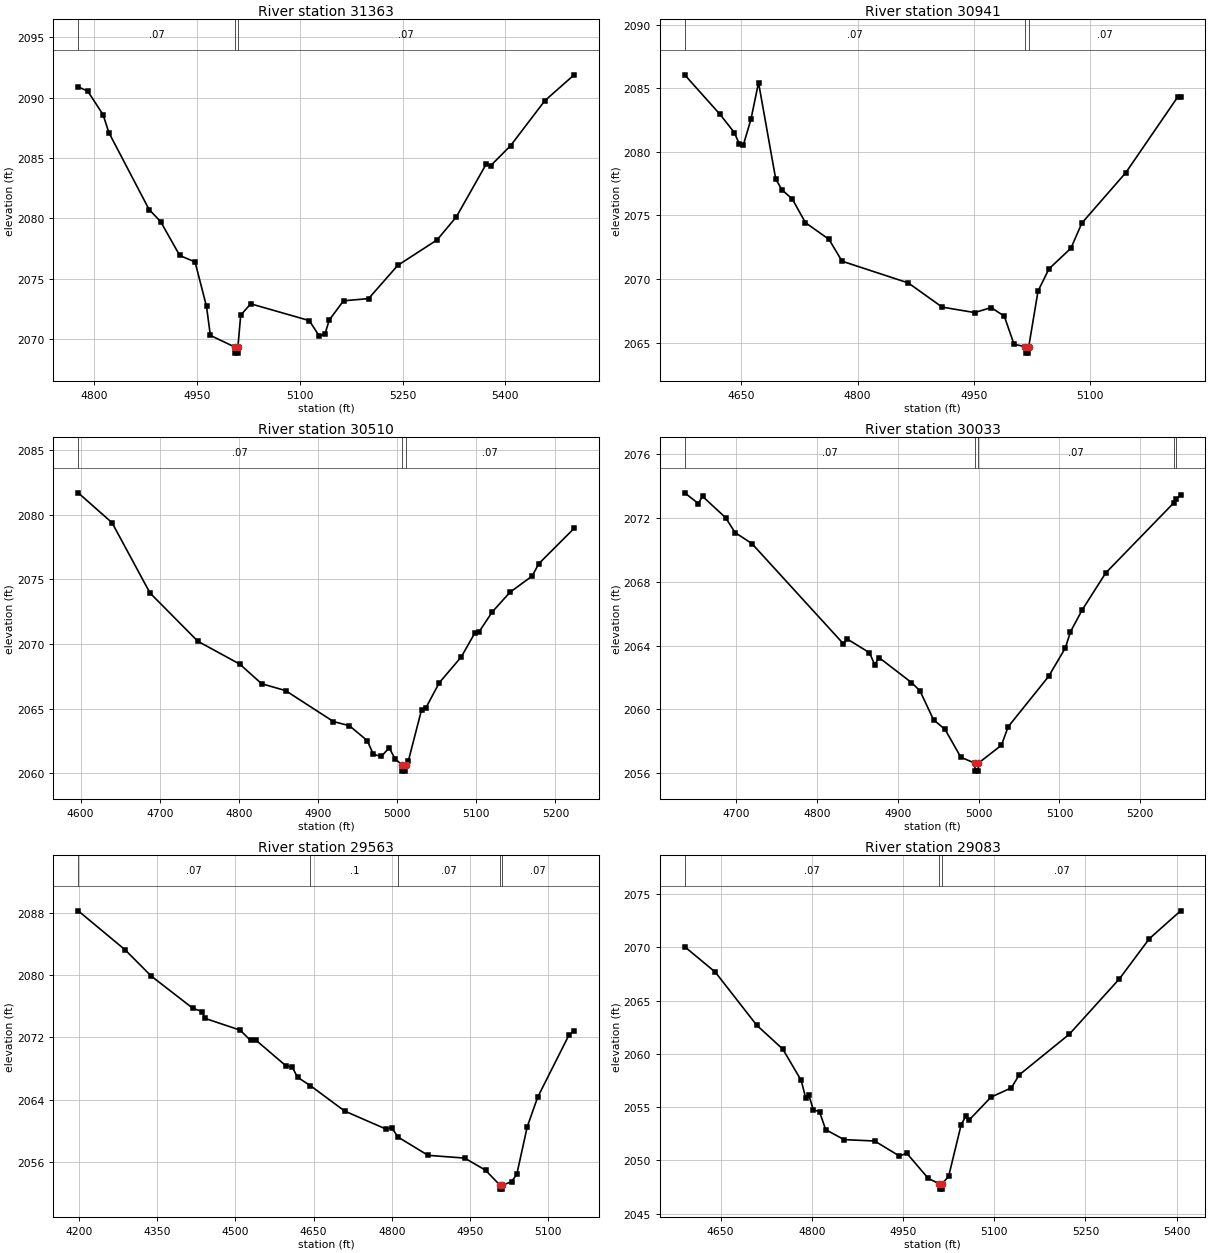
Type RM Length L Ch R = 1 ,31363   ,422,422,422
BEGIN DESCRIPTION:
Dry Branch 60.0
END DESCRIPTION:
XS GIS Cut Line= 3
      1877524.97     13981225.01        1877325.       13981325.
      1876924.98     13981625.01
#Sta/Elev= 30
  4776.7  2090.9  4790.6 2090.55    4813 2088.59  4821.4 2087.11  4880.1 2080.73
  4896.9 2079.73  4924.8 2076.92  4947.2 2076.38  4963.9 2072.69  4969.5 2070.29
  5005.4 2069.32  5005.7 2068.82  5009.4 2068.82  5009.7 2069.32  5013.8 2071.97
  5028.4 2072.91  5113.8 2071.52  5128.4 2070.24  5136.7 2070.39    5143 2071.57
  5163.8 2073.16  5200.3 2073.34    5243  2076.1  5300.3 2078.21  5328.4 2080.12
  5372.2 2084.52  5378.4 2084.36  5407.6 2086.03  5457.6 2089.76  5500.3  2091.9
#Mann= 3 ,-1 , 0
  4776.7     .07       0  5005.4     .05       0  5009.7     .07       0
Bank Sta=5005.4,5009.7
XS Rating Curve= 0 ,0
Exp/Cntr=0.3,0.1

Type RM Length L Ch R = 1 ,30941   ,431,431,431
BEGIN DESCRIPTION:
Dry Branch 59.0
END DESCRIPTION:
XS GIS Cut Line= 3
      1877374.97     13980975.01        1876975.       13981125.
        1876825.       13981275.
#Sta/Elev= 30
  4577.1 2086.06  4622.5 2082.96  4641.1 2081.52  4647.4 2080.64  4652.7 2080.54
  4662.5 2082.55  4672.3 2085.45  4694.5 2077.85  4702.6 2077.01  4715.9 2076.28
  4732.8 2074.43  4763.1 2073.12    4780  2071.4  4865.4 2069.69    4909 2067.79
  4950.9 2067.36  4972.2 2067.75  4989.1 2067.08  5001.6 2064.87  5016.3 2064.67
  5016.6 2064.17  5020.3 2064.17  5020.6 2064.67  5032.6 2069.05  5046.7  2070.8
    5075 2072.42  5089.1  2074.4  5145.7 2078.36  5212.9 2084.34  5216.4 2084.34
#Mann= 3 ,-1 , 0
  4577.1     .07       0  5016.3     .05       0  5020.6     .07       0
Bank Sta=5016.3,5020.6
XS Rating Curve= 0 ,0
Exp/Cntr=0.3,0.1

Type RM Length L Ch R = 1 ,30510   ,477,477,477
BEGIN DESCRIPTION:
Dry Branch 58.0
END DESCRIPTION:
XS GIS Cut Line= 3
        1877275.       13980675.        1876875.       13980725.
      1876675.02     13980824.99
#Sta/Elev= 30
  4596.9 2081.71  4639.7 2079.39  4687.6 2073.95  4748.1 2070.21    4801 2068.44
  4828.7 2066.92  4858.9 2066.39  4919.4 2063.99  4939.5 2063.67  4962.2 2062.51
  4969.8 2061.45  4979.9 2061.29  4989.9 2061.96  4997.5 2061.07  5006.2 2060.65
  5006.5 2060.15  5010.3 2060.15  5010.6 2060.65    5014 2060.92  5030.8 2064.91
  5036.4 2065.07  5053.1 2066.99  5081.1 2069.01  5097.8 2070.82  5103.4 2070.94
  5120.2 2072.49  5142.6 2074.01  5170.5 2075.26  5178.9 2076.22  5223.6 2078.96
#Mann= 3 ,-1 , 0
  4596.9     .07       0  5006.2     .05       0  5010.6     .07       0
Bank Sta=5006.2,5010.6
XS Rating Curve= 0 ,0
Exp/Cntr=0.3,0.1

Type RM Length L Ch R = 1 ,30033   ,470,470,470
BEGIN DESCRIPTION:
Dry Branch 57.0
END DESCRIPTION:
XS GIS Cut Line= 3
        1877025.       13980225.        1876675.       13980325.
      1876475.01     13980474.99
#Sta/Elev= 30
    4636 2073.57  4652.9  2072.9  4658.1 2073.35  4686.7 2072.01  4698.4 2071.08
  4719.2 2070.39  4832.3 2064.12  4837.5  2064.4  4864.8 2063.55  4871.3 2062.79
  4876.5 2063.25  4916.8 2061.68  4927.2 2061.17  4944.1 2059.35  4958.4 2058.74
  4977.9    2057  4995.2 2056.63  4995.5 2056.13  4999.3 2056.13  4999.6 2056.63
  5028.1 2057.75  5036.5 2058.91  5086.5 2062.06  5107.3 2063.85  5113.6 2064.86
  5128.1 2066.23  5157.3 2068.55  5241.7 2072.95  5244.3 2073.16    5250 2073.42
#Mann= 5 ,-1 , 0
    4636     .07       0  4995.2     .05       0  4999.6     .07       0
  5241.7    .035       0  5244.3     .07       0
Bank Sta=4995.2,4999.6
XS Rating Curve= 0 ,0
Exp/Cntr=0.3,0.1

Type RM Length L Ch R = 1 ,29563   ,480,480,480
BEGIN DESCRIPTION:
Dry Branch 56.0
END DESCRIPTION:
XS GIS Cut Line= 3
      1877274.96       13979975.        1876475.       13979925.
      1876325.02       13979925.
#Sta/Elev= 30
  4198.4 2088.26  4288.5 2083.24  4338.6 2079.87  4418.8 2075.71  4436.3 2075.32
  4441.3 2074.45    4509 2072.93    4529 2071.61    4539 2071.66  4596.6 2068.36
  4609.2 2068.16  4619.2 2066.87  4643.8  2065.8  4709.4 2062.54  4789.5  2060.2
  4799.5 2060.41  4812.2 2059.18  4869.7 2056.84  4939.8 2056.49  4979.9 2054.93
  5007.7    2053    5008  2052.5  5011.9  2052.5  5012.2    2053  5029.9 2053.46
  5039.9 2054.42  5059.9 2060.51  5079.9 2064.31  5139.9 2072.29  5149.9 2072.83
#Mann= 5 ,-1 , 0
  4198.4     .07       0  4643.8      .1       0  4812.2     .07       0
  5007.7     .05       0  5012.2     .07       0
Bank Sta=5007.7,5012.2
XS Rating Curve= 0 ,0
Exp/Cntr=0.3,0.1

Type RM Length L Ch R = 1 ,29083   ,419,419,419
BEGIN DESCRIPTION:
Dry Branch 55.0
END DESCRIPTION:
XS GIS Cut Line= 3
      1876974.97       13979425.        1876575.       13979475.
        1876175.       13979575.
#Sta/Elev= 30
    4591 2070.07  4641.4 2067.68  4709.4  2062.7  4752.2 2060.46  4782.5 2057.52
    4790 2055.85    4795 2056.14  4802.6 2054.75  4812.7 2054.57  4822.8 2052.89
    4853 2051.95  4903.4 2051.82  4943.7 2050.42  4956.3 2050.66  4991.6  2048.3
  5009.8  2047.8  5010.2  2047.3  5014.1  2047.3  5014.4  2047.8    5025 2048.51
  5045.6 2053.35  5053.4 2054.18  5058.5 2053.78  5094.6 2055.94  5128.1 2056.81
    5141 2058.03  5223.4 2061.85  5305.9 2067.06  5354.9 2070.82  5406.4 2073.44
#Mann= 3 ,-1 , 0
    4591     .07       0  5009.8     .05       0  5014.4     .07       0
Bank Sta=5009.8,5014.4
XS Rating Curve= 0 ,0
Exp/Cntr=0.3,0.1

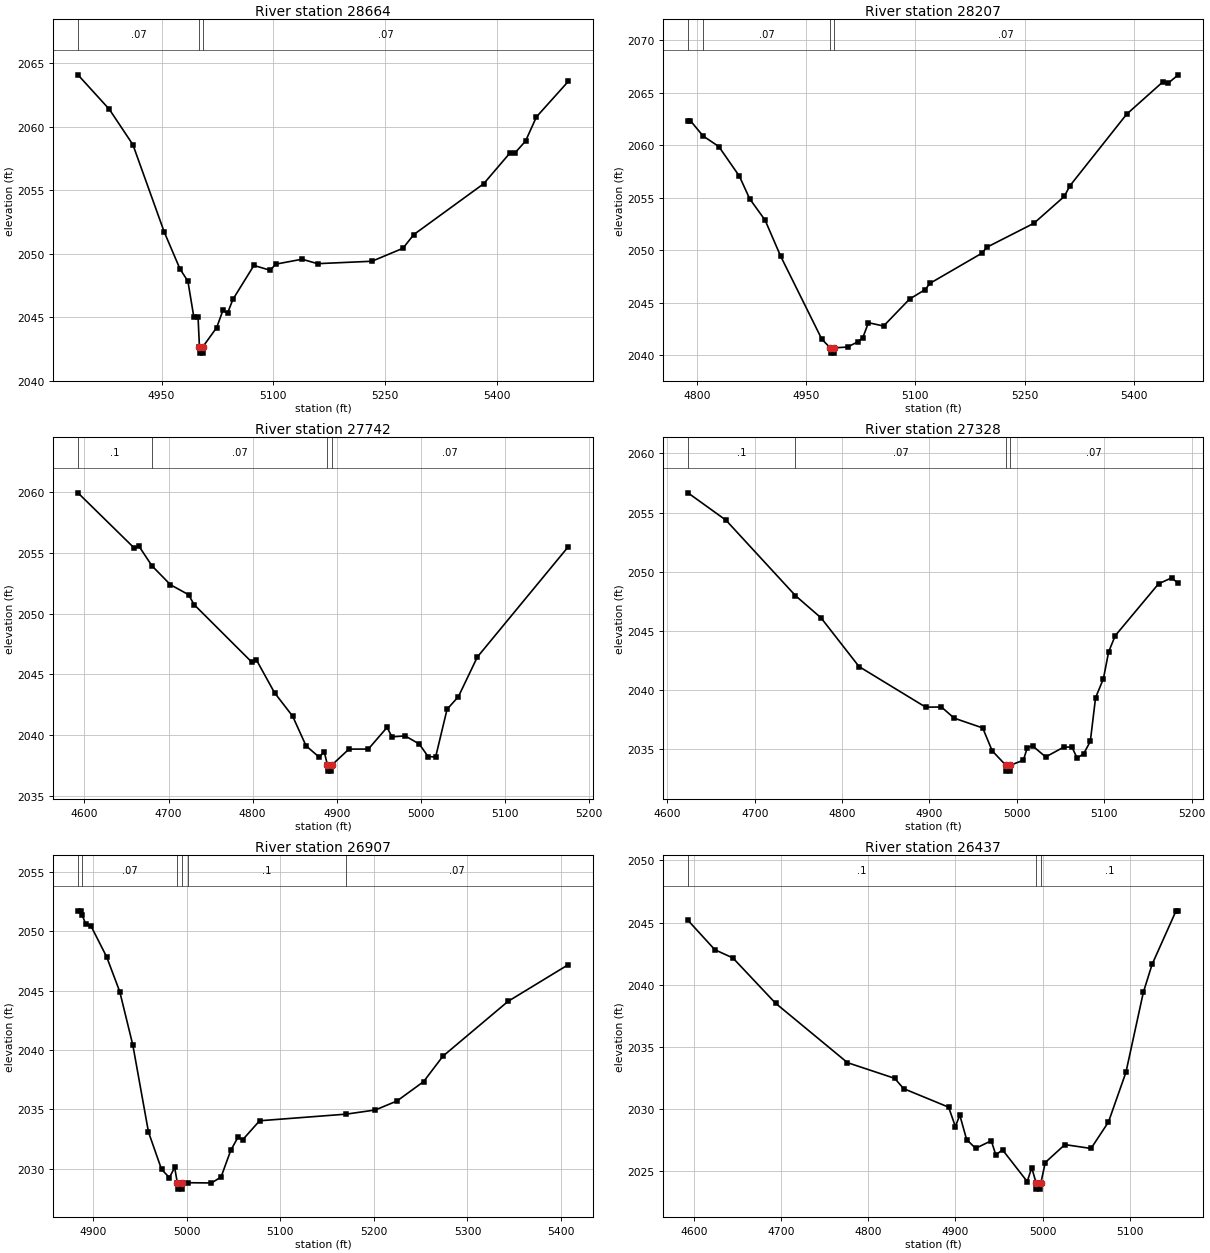
Type RM Length L Ch R = 1 ,28664   ,457,457,457
BEGIN DESCRIPTION:
Dry Branch 54.0
END DESCRIPTION:
XS GIS Cut Line= 3
      1876824.98     13979174.99        1876675.       13979125.
      1876274.99       13979425.
#Sta/Elev= 30
  4837.8 2064.08  4879.9 2061.37  4911.6 2058.58  4953.7  2051.7  4974.8  2048.8
  4985.4 2047.84  4993.3 2045.04    4999 2045.04  5000.9 2042.68  5001.2 2042.18
  5005.2 2042.18  5005.5 2042.68    5024 2044.19  5032.4 2045.54  5038.6 2045.33
  5045.9 2046.42    5074 2049.08  5095.9  2048.7  5103.2 2049.18  5138.6 2049.57
  5159.4 2049.22  5232.4 2049.41    5274 2050.43  5288.6 2051.51  5382.4 2055.51
  5417.8 2057.94    5424 2057.91  5438.6 2058.87  5453.2 2060.77  5495.9 2063.56
#Mann= 3 ,-1 , 0
  4837.8     .07       0  5000.9     .05       0  5005.5     .07       0
Bank Sta=5000.9,5005.5
XS Rating Curve= 0 ,0
Exp/Cntr=0.3,0.1

Type RM Length L Ch R = 1 ,28207   ,465,465,465
BEGIN DESCRIPTION:
Dry Branch 53.0
END DESCRIPTION:
XS GIS Cut Line= 3
      1876474.98     13978725.02        1876325.       13978875.
      1876024.99     13979225.02
#Sta/Elev= 30
  4787.9 2062.34  4791.4 2062.34  4808.8 2060.89  4830.3 2059.89  4858.6 2057.06
  4872.7 2054.91  4893.9 2052.87  4915.1 2049.46  4971.7 2041.54  4983.3 2040.71
  4983.7 2040.21  4988.1 2040.21  4988.5 2040.71  5007.1 2040.79  5021.4  2041.3
    5028 2041.68  5035.7 2043.11  5056.5 2042.79  5092.2 2045.36  5113.6 2046.26
  5120.2 2046.86  5191.5 2049.73  5198.1 2050.29  5262.9 2052.58  5304.6 2055.14
  5312.3 2056.15  5390.2 2062.97  5439.6 2066.03  5447.3 2065.93    5461 2066.72
#Mann= 4 ,-1 , 0
  4787.9      .1       0  4808.8     .07       0  4983.3     .05       0
  4988.5     .07       0
Bank Sta=4983.3,4988.5
XS Rating Curve= 0 ,0
Exp/Cntr=0.3,0.1

Type RM Length L Ch R = 1 ,27742   ,414,414,414
BEGIN DESCRIPTION:
Dry Branch 52.0
END DESCRIPTION:
XS GIS Cut Line= 3
        1876275.       13978475.        1875925.       13978675.
      1875824.99     13978825.01
#Sta/Elev= 30
  4592.2 2059.92  4659.1 2055.39  4664.9 2055.53  4680.2 2053.93  4702.3 2052.37
  4723.9 2051.55  4730.4 2050.74  4798.8 2046.03  4804.6 2046.19  4826.1  2043.5
  4847.7 2041.57  4863.6 2039.14  4879.4  2038.2  4885.2 2038.66  4889.1 2037.56
  4889.5 2037.06  4893.9 2037.06  4894.3 2037.56  4914.7 2038.87  4937.7 2038.87
    4960 2040.65  4965.8 2039.88  4981.6 2039.95  4998.3 2039.29  5008.8 2038.26
  5017.8 2038.22  5031.4 2042.14  5044.9 2043.18  5067.4 2046.43  5175.6 2055.49
#Mann= 4 ,-1 , 0
  4592.2      .1       0  4680.2     .07       0  4889.1     .05       0
  4894.3     .07       0
Bank Sta=4889.1,4894.3
XS Rating Curve= 0 ,0
Exp/Cntr=0.3,0.1

Type RM Length L Ch R = 1 ,27328   ,421,421,421
BEGIN DESCRIPTION:
Dry Branch 51.0
END DESCRIPTION:
XS GIS Cut Line= 3
      1876124.98     13978225.01        1875775.       13978375.
      1875675.03     13978524.96
#Sta/Elev= 30
  4623.6 2056.67  4667.1 2054.36  4746.6 2047.98  4775.9  2046.1  4819.4 2041.98
  4895.6 2038.55  4913.7 2038.56  4928.2 2037.62  4960.9 2036.79  4971.7 2034.86
  4987.3 2033.64  4987.7 2033.14  4992.1 2033.14  4992.5 2033.64  5007.4 2034.06
  5011.9 2035.12  5017.9 2035.28  5032.9 2034.34  5053.9 2035.18    5063 2035.17
    5069 2034.23  5076.5 2034.63    5084 2035.65    5090 2039.34    5099 2040.96
    5105 2043.23  5112.5 2044.59  5162.1 2048.98  5177.1 2049.48  5184.6 2049.01
#Mann= 4 ,-1 , 0
  4623.6      .1       0  4746.6     .07       0  4987.3     .05       0
  4992.5     .07       0
Bank Sta=4987.3,4992.5
XS Rating Curve= 0 ,0
Exp/Cntr=0.3,0.1

Type RM Length L Ch R = 1 ,26907   ,470,470,470
BEGIN DESCRIPTION:
Dry Branch 50.0
END DESCRIPTION:
XS GIS Cut Line= 3
      1875475.02     13977975.04        1875525.       13978075.
      1875625.01     13978475.02
#Sta/Elev= 30
  4883.6 2051.74  4886.4 2051.74  4888.3 2051.35  4891.9 2050.62  4897.5 2050.47
  4914.3 2047.86  4928.3 2044.93  4942.3 2040.42    4959  2033.1    4973 2029.95
  4981.4 2029.26    4987 2030.12  4989.9 2028.79  4990.3 2028.29  4994.9 2028.29
  4995.3 2028.79  5000.9 2028.83  5026.3 2028.81  5036.6 2029.31  5046.9 2031.55
  5054.6 2032.65  5059.8 2032.46  5077.8 2034.05  5170.5 2034.61  5201.5 2034.96
  5224.7 2035.72  5253.1 2037.35  5273.7 2039.49  5343.3 2044.11  5407.7  2047.2
#Mann= 6 ,-1 , 0
  4883.6      .1       0  4888.3     .07       0  4989.9     .05       0
  4995.3     .07       0  5000.9      .1       0  5170.5     .07       0
Bank Sta=4989.9,4995.3
XS Rating Curve= 0 ,0
Exp/Cntr=0.3,0.1

Type RM Length L Ch R = 1 ,26437   ,473,473,473
BEGIN DESCRIPTION:
Dry Branch 49.0
END DESCRIPTION:
XS GIS Cut Line= 3
      1875275.01     13977974.97        1875175.       13978375.
        1875175.     13978524.96
#Sta/Elev= 30
  4593.2 2045.19  4624.1 2042.82  4644.8 2042.16  4693.7 2038.52  4776.2 2033.74
  4830.3 2032.48  4840.6 2031.65  4892.2 2030.16  4899.9  2028.6    4905 2029.52
  4912.8 2027.56  4923.1 2026.85  4941.1 2027.46  4946.3 2026.32    4954 2026.73
  4982.3 2024.18  4987.5 2025.29  4992.5 2024.07  4992.9 2023.57  4997.5 2023.57
    4998 2024.07    5003 2025.71  5025.5 2027.15  5055.5 2026.84  5075.5 2028.97
  5095.5 2032.96  5115.5  2039.4  5125.5 2041.64    5153 2045.95  5155.5 2045.95
#Mann= 3 ,-1 , 0
  4593.2      .1       0  4992.5     .05       0    4998      .1       0
Bank Sta=4992.5,4998
XS Rating Curve= 0 ,0
Exp/Cntr=0.3,0.1

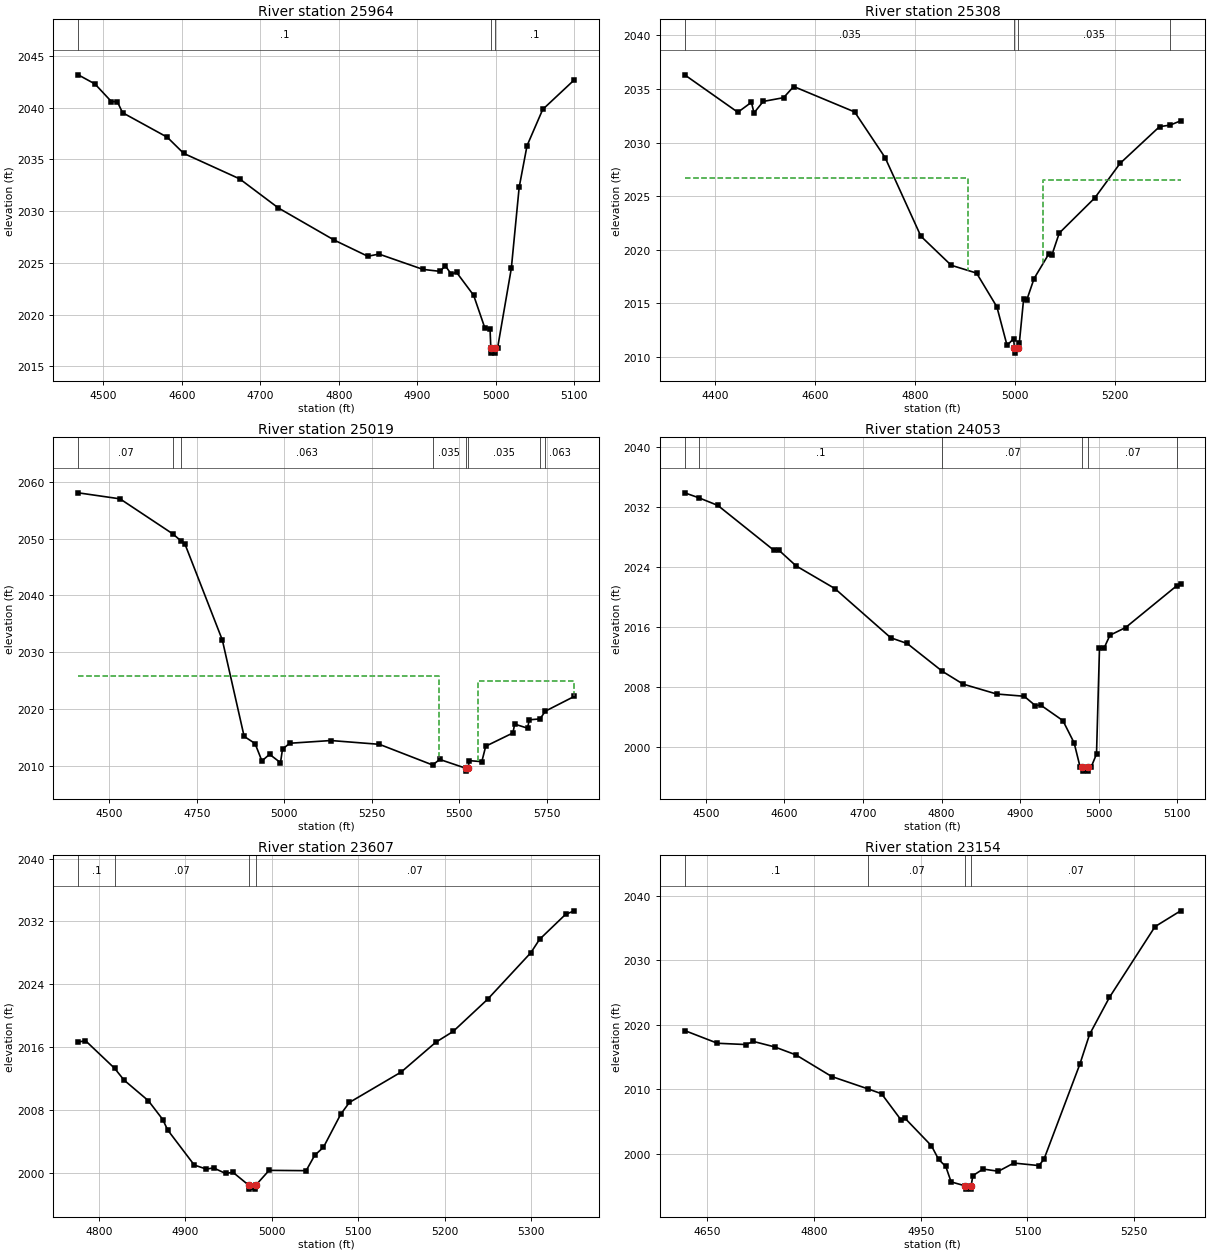
Type RM Length L Ch R = 1 ,25964   ,656,656,656
BEGIN DESCRIPTION:
Dry Branch 48.0
END DESCRIPTION:
XS GIS Cut Line= 3
      1875174.99     13977925.01        1874775.       13978275.
        1874775.     13978375.01
#Sta/Elev= 30
  4468.2 2043.16  4489.5 2042.28  4510.4 2040.58    4518 2040.56  4524.7  2039.5
  4581.6 2037.13  4602.5 2035.57  4673.7 2033.11    4723  2030.3  4794.2 2027.19
  4836.9 2025.63  4851.2 2025.84  4907.2 2024.36    4929 2024.17  4935.6 2024.71
  4943.2  2023.9  4949.9 2024.08  4971.7 2021.86  4985.9 2018.72  4992.6 2018.59
  4993.6 2016.77  4994.1 2016.27  4998.7 2016.27  4999.1 2016.77  5002.2 2016.77
  5019.7 2024.46  5029.7  2032.3  5039.7 2036.31  5059.7 2039.82  5099.7 2042.66
#Mann= 3 ,-1 , 0
  4468.2      .1       0  4993.6     .05       0  4999.1      .1       0
Bank Sta=4993.6,4999.1
XS Rating Curve= 0 ,0
Exp/Cntr=0.3,0.1

Type RM Length L Ch R = 1 ,25308   ,289,289,289
BEGIN DESCRIPTION:
Dry Branch 47.0
END DESCRIPTION:
XS GIS Cut Line= 3
      1875029.65     13977655.56      1874385.65     13977773.71
      1874110.68       13977970.
#Sta/Elev= 30
  4339.6 2036.31    4446 2032.82  4473.2 2033.75  4478.3 2032.76  4496.8 2033.83
  4537.5 2034.18  4557.8 2035.22  4679.8 2032.85  4740.8 2028.59  4812.3 2021.27
    4873 2018.56  4923.8 2017.83  4964.5 2014.68  4984.8 2011.09  4997.8 2011.71
  4999.7 2010.87  5000.2 2010.37  5006.7 2010.87  5009.4 2011.32    5018 2015.43
  5024.1  2015.3  5038.9 2017.32  5068.4 2019.62  5074.5 2019.51  5089.3 2021.56
  5160.5 2024.84  5210.9 2028.05    5290 2031.48  5310.9 2031.62  5332.2 2032.02
#Mann= 4 ,-1 , 0
  4339.6    .035       0  4999.7    .035       0  5006.7    .035       0
  5310.9      .1       0
#XS Ineff= 2 , 0
         4907.61 2026.67 5056.26         2026.52
Permanent Ineff=
       F       F
Bank Sta=4999.7,5006.7
XS Rating Curve= 0 ,0
Exp/Cntr=0.3,0.1

Type RM Length L Ch R = 1 ,25019   ,966,966,966
BEGIN DESCRIPTION:
Dry Branch 46.0
END DESCRIPTION:
XS GIS Cut Line= 3
      1874791.49     13977386.61      1874228.83     13977545.05
      1873419.39     13977741.12
#Sta/Elev= 30
  4411.2 2058.07  4530.7 2057.01  4681.5 2050.84  4705.2 2049.59  4716.5 2049.01
  4823.1 2032.14  4885.4 2015.17  4916.6 2013.91  4936.2 2010.85  4958.2 2012.01
  4989.3 2010.54  4995.1 2012.94    5016 2013.96  5133.4 2014.44    5272 2013.77
  5424.2 2010.13  5444.4 2011.11  5519.3 2009.55  5519.8 2009.05  5526.5 2009.55
    5528  2010.9  5564.7 2010.72  5575.9 2013.44  5653.5 2015.77  5658.6 2017.33
  5695.3 2016.62  5700.5 2018.09    5731 2018.25  5746.5 2019.62  5828.6  2022.2
#Mann= 8 ,-1 , 0
  4411.2     .07       0  4681.5    .035       0  4705.2    .063       0
  5424.2    .035       0  5519.3     .05       0  5526.5    .035       0
    5731     .07       0  5746.5    .063       0
#XS Ineff= 2 , 0
         5442.58 2025.88 5554.06            2025
Permanent Ineff=
       F       F
Bank Sta=5519.3,5526.5
XS Rating Curve= 0 ,0
Exp/Cntr=0.3,0.1

Type RM Length L Ch R = 1 ,24053   ,446,446,446
BEGIN DESCRIPTION:
Dry Branch 44.0
END DESCRIPTION:
XS GIS Cut Line= 3
      1873724.98     13977225.03        1873375.       13977625.
        1873375.     13977725.03
#Sta/Elev= 30
  4472.9 2033.91  4490.9 2033.25  4515.1 2032.23  4586.3 2026.26  4592.9 2026.25
  4614.8 2024.16  4664.1 2021.14  4735.3 2014.57  4756.2 2013.81  4801.1 2010.09
  4827.4 2008.39  4870.1 2007.07  4905.2 2006.77  4919.4 2005.52  4926.1  2005.6
  4954.5 2003.52  4968.8 2000.55  4976.4 1997.33  4979.3 1997.28  4979.8 1996.78
  4986.2 1996.78  4986.7 1997.28  4990.6 1997.35  4997.3 1999.06  5001.1 2013.19
  5006.9 2013.19  5014.4 2014.91  5034.4 2015.94  5099.2 2021.49  5104.4 2021.72
#Mann= 6 ,-1 , 0
  4472.9    .035       0  4490.9      .1       0  4801.1     .07       0
  4979.3     .05       0  4986.7     .07       0  5099.2    .063       0
Bank Sta=4979.3,4986.7
XS Rating Curve= 0 ,0
Exp/Cntr=0.3,0.1

Type RM Length L Ch R = 1 ,23607   ,453,453,453
BEGIN DESCRIPTION:
Dry Branch 43.0
END DESCRIPTION:
XS GIS Cut Line= 3
        1873125.     13977174.99        1873025.       13977375.
      1872675.02       13977375.
#Sta/Elev= 30
  4776.3 2016.64  4784.7 2016.82  4818.3 2013.31  4829.4 2011.79  4857.4 2009.18
  4874.1 2006.78  4879.7 2005.46  4910.5 2000.99  4924.5 2000.47  4932.8 2000.62
  4946.8 1999.91  4955.2 2000.07  4973.5 1998.42    4974 1997.92  4981.2 1997.92
  4981.7 1998.42  4997.1 2000.31  5039.9 2000.27  5049.9 2002.24  5059.9 2003.24
  5079.9 2007.45  5089.9 2008.95  5149.9 2012.83  5189.9 2016.62  5209.9 2017.99
  5249.9  2022.1  5299.9 2028.03  5309.9 2029.72  5339.9 2032.89  5349.9 2033.35
#Mann= 4 ,-1 , 0
  4776.3      .1       0  4818.3     .07       0  4973.5     .05       0
  4981.7     .07       0
Bank Sta=4973.5,4981.7
XS Rating Curve= 0 ,0
Exp/Cntr=0.3,0.1

Type RM Length L Ch R = 1 ,23154   ,466,466,466
BEGIN DESCRIPTION:
Dry Branch 42.0
END DESCRIPTION:
XS GIS Cut Line= 3
      1873201.03     13977051.78        1872825.       13977025.
      1872575.03     13977224.98
#Sta/Elev= 30
  4618.2  2019.1  4664.3 2017.13  4704.4 2016.93  4714.5 2017.42  4744.5 2016.57
  4774.6 2015.33  4824.8 2011.98  4875.6 2010.07  4894.9 2009.31  4922.4 2005.24
  4927.4 2005.57  4965.1 2001.24  4975.1 1999.14  4985.2 1998.04  4992.7 1995.65
  5012.7 1995.03  5013.2 1994.53  5020.4 1994.53  5020.9 1995.03  5023.2 1996.61
  5037.6 1997.64  5059.2  1997.3  5080.8 1998.57    5116 1998.18  5123.2 1999.15
  5173.7  2013.9  5187.3  2018.5  5215.3 2024.25  5279.3  2035.2  5315.3 2037.65
#Mann= 4 ,-1 , 0
  4618.2      .1       0  4875.6     .07       0  5012.7     .05       0
  5020.9     .07       0
Bank Sta=5012.7,5020.9
XS Rating Curve= 0 ,0
Exp/Cntr=0.3,0.1

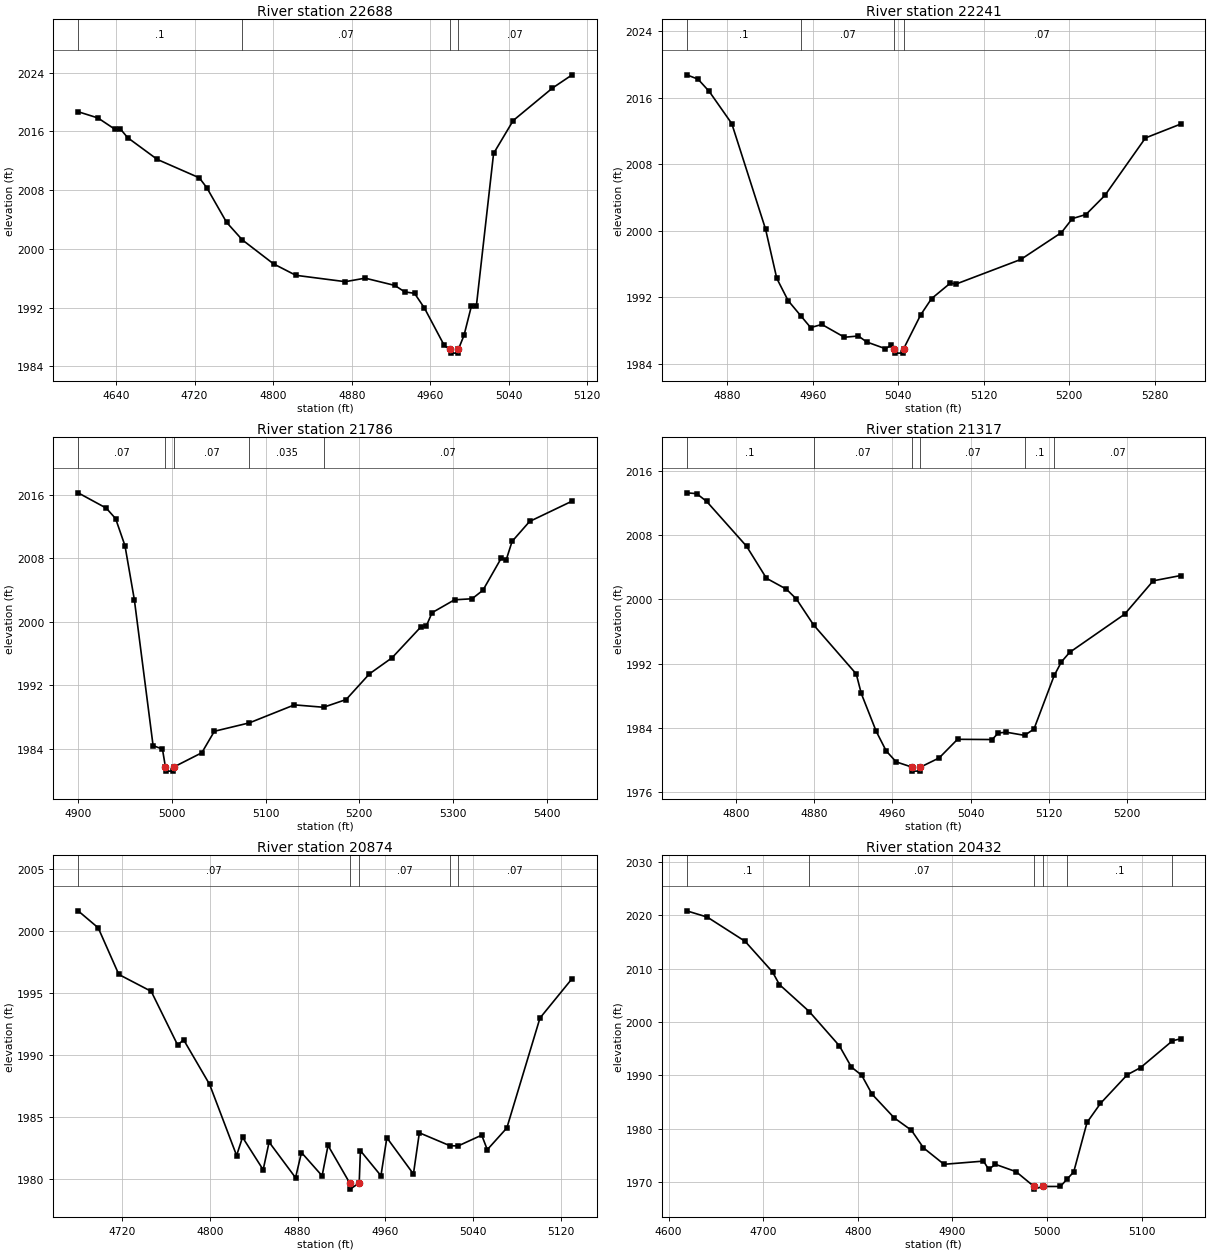
Type RM Length L Ch R = 1 ,22688   ,447,447,447
BEGIN DESCRIPTION:
Dry Branch 41.0
END DESCRIPTION:
XS GIS Cut Line= 3
      1873124.99       13976675.        1872725.       13976625.
      1872625.01       13976625.
#Sta/Elev= 30
  4601.4 2018.69  4621.6 2017.84  4639.2 2016.27  4644.2 2016.38  4651.8 2015.16
    4682 2012.19  4724.8 2009.68  4732.4 2008.34  4752.6 2003.61  4768.6 2001.22
  4800.4 1997.95  4823.1 1996.39  4873.5 1995.52  4893.7    1996  4923.9 1995.01
    4934 1994.13    4944 1993.93  4954.1 1991.92  4974.3 1986.82  4980.2 1986.28
  4980.7 1985.78  4988.1 1985.78  4988.6 1986.28  4994.4 1988.21    5002 1992.24
    5007 1992.24  5024.5    2013  5044.5 2017.49  5084.5 2021.92  5104.5 2023.72
#Mann= 4 ,-1 , 0
  4601.4      .1       0  4768.6     .07       0  4980.2     .05       0
  4988.6     .07       0
Bank Sta=4980.2,4988.6
XS Rating Curve= 0 ,0
Exp/Cntr=0.3,0.1

Type RM Length L Ch R = 1 ,22241   ,455,455,455
BEGIN DESCRIPTION:
Dry Branch 40.0
END DESCRIPTION:
XS GIS Cut Line= 3
      1873125.01       13976325.        1872975.       13976275.
      1872674.97     13976325.01
#Sta/Elev= 30
  4841.9 2018.73  4852.5 2018.21    4863 2016.73  4884.1 2012.86  4915.7 2000.17
  4926.2 1994.25  4936.8 1991.58  4948.8 1989.73  4957.9 1988.33  4968.4 1988.71
  4989.5 1987.17  5002.6 1987.32  5010.2 1986.61  5027.9 1985.79    5033 1986.19
  5036.3 1985.76  5036.8 1985.26  5044.3 1985.26  5044.8 1985.76  5060.9 1989.87
    5071 1991.81  5088.7 1993.69  5093.8 1993.56  5154.6 1996.53  5192.6 1999.76
  5202.8 2001.44  5215.5 2001.93  5233.2 2004.22  5271.2 2011.14  5304.2 2012.81
#Mann= 4 ,-1 , 0
  4841.9      .1       0  4948.8     .07       0  5036.3     .05       0
  5044.8     .07       0
Bank Sta=5036.3,5044.8
XS Rating Curve= 0 ,0
Exp/Cntr=0.3,0.1

Type RM Length L Ch R = 1 ,21786   ,469,469,469
BEGIN DESCRIPTION:
Dry Branch 39.0
END DESCRIPTION:
XS GIS Cut Line= 3
        1873125.       13975875.        1873025.       13975875.
        1872625.       13976025.
#Sta/Elev= 30
    4900 2016.22    4930  2014.3    4940 2012.98    4950 2009.57    4960 2002.79
    4980 1984.44    4990    1984  4993.2 1981.73  4993.7 1981.23  5001.3 1981.23
  5001.8 1981.73    5032 1983.54  5045.4 1986.24  5082.8  1987.3  5130.8 1989.56
  5161.9 1989.26    5186 1990.23  5210.9 1993.46    5235 1995.48  5266.1  1999.4
  5271.5 1999.45  5277.7 2001.15  5301.7 2002.77  5320.4  2002.9    5332 2003.97
  5351.6 2008.02  5356.9 2007.81  5363.1 2010.11  5381.8 2012.62  5427.2 2015.18
#Mann= 5 ,-1 , 0
    4900     .07       0  4993.2     .05       0  5001.8     .07       0
  5082.8    .035       0  5161.9     .07       0
Bank Sta=4993.2,5001.8
XS Rating Curve= 0 ,0
Exp/Cntr=0.3,0.1

Type RM Length L Ch R = 1 ,21317   ,443,443,443
BEGIN DESCRIPTION:
Dry Branch 38.0
END DESCRIPTION:
XS GIS Cut Line= 3
      1873074.96     13975425.01        1872825.       13975475.
      1872625.01     13975624.99
#Sta/Elev= 30
  4749.8 2013.25    4760 2013.15  4770.2 2012.18    4811  2006.6  4831.3 2002.62
  4851.7 2001.26  4861.9 2000.04  4879.5 1996.81  4923.1 1990.71  4928.2 1988.29
  4943.5 1983.57  4953.7 1981.13  4963.9 1979.77    4980 1979.12  4980.5 1978.62
  4988.2 1978.62  4988.7 1979.12  5007.8 1980.26  5026.6 1982.58    5062 1982.55
  5068.3 1983.37  5076.6 1983.46  5095.1 1983.07  5104.7 1983.85  5125.4 1990.52
  5132.8 1992.22  5141.2  1993.4  5197.4 1998.15  5226.6  2002.3  5254.7 2002.96
#Mann= 6 ,-1 , 0
  4749.8      .1       0  4879.5     .07       0    4980     .05       0
  4988.7     .07       0  5095.1      .1       0  5125.4     .07       0
Bank Sta=4980,4988.7
XS Rating Curve= 0 ,0
Exp/Cntr=0.3,0.1

Type RM Length L Ch R = 1 ,20874   ,442,442,442
BEGIN DESCRIPTION:
Dry Branch 37.0
END DESCRIPTION:
XS GIS Cut Line= 3
        1872922.     13975244.82        1872625.       13975125.
      1872495.81     13975138.05
#Sta/Elev= 30
  4680.1 2001.63  4698.4 2000.26  4717.2  1996.5  4746.7 1995.14  4770.8 1990.81
  4776.2 1991.24  4799.9 1987.64  4824.5 1981.91  4829.9 1983.38  4848.7 1980.76
  4854.1 1982.99  4878.2 1980.12  4883.6 1982.15  4902.4 1980.27  4907.8 1982.72
  4927.5  1979.7    4928  1979.2  4936.2  1979.7  4937.3  1982.3    4956 1980.28
  4961.4 1983.34  4985.6 1980.42    4991 1983.74  5018.8  1982.7  5026.3 1982.68
  5047.8 1983.55  5052.9 1982.38  5070.7 1984.13  5100.9 1992.99  5130.2 1996.17
#Mann= 5 ,-1 , 0
  4680.1     .07       0  4927.5     .05       0  4936.2     .07       0
  5018.8    .035       0  5026.3     .07       0
Bank Sta=4927.5,4936.2
XS Rating Curve= 0 ,0
Exp/Cntr=0.3,0.1

Type RM Length L Ch R = 1 ,20432   ,430,430,430
BEGIN DESCRIPTION:
Dry Branch 36.0
END DESCRIPTION:
XS GIS Cut Line= 3
      1872575.01     13974424.97        1872425.       13974775.
      1872325.03     13974874.97
#Sta/Elev= 30
  4619.1 2020.86  4640.9 2019.68  4680.8 2015.14  4709.8 2009.39  4717.1 2007.02
  4748.6 2001.96  4780.5 1995.52  4793.2 1991.53  4804.1 1989.99    4815 1986.45
  4838.5 1981.99  4856.7 1979.66  4869.4 1976.36  4891.1 1973.28  4932.8 1973.88
  4938.3 1972.34  4945.5 1973.27  4967.3 1971.89  4986.2 1969.12  4986.7 1968.62
  4995.5 1969.12  5014.1 1969.12  5020.9 1970.44  5028.2 1971.85  5042.3 1981.15
  5056.5 1984.71  5084.8 1990.09  5098.9 1991.43  5132.6 1996.47  5141.3 1996.84
#Mann= 6 ,-1 , 0
  4619.1      .1       0  4748.6     .07       0  4986.2     .05       0
  4995.5     .07       0  5020.9      .1       0  5132.6     .07       0
Bank Sta=4986.2,4995.5
XS Rating Curve= 0 ,0
Exp/Cntr=0.3,0.1

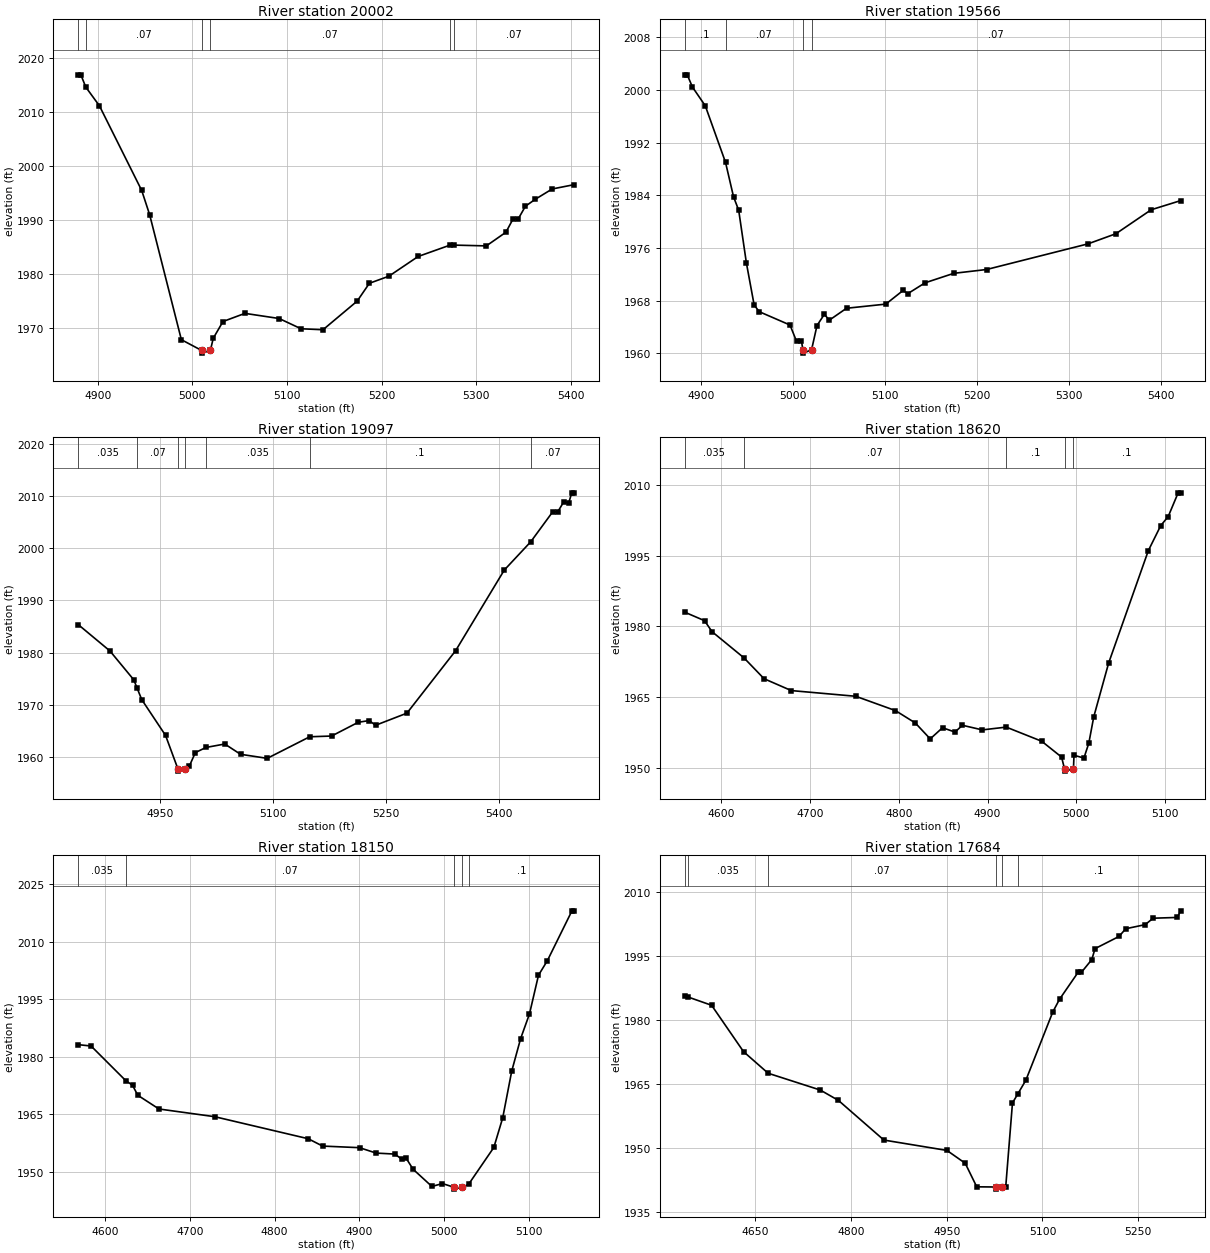
Type RM Length L Ch R = 1 ,20002   ,436,436,436
BEGIN DESCRIPTION:
Dry Branch 35.0
END DESCRIPTION:
XS GIS Cut Line= 3
        1872325.     13974324.99        1872275.       13974425.
        1872175.     13974824.98
#Sta/Elev= 30
  4879.4 2016.88  4882.2 2016.88  4887.4 2014.61  4901.8 2011.15  4946.5 1995.47
  4954.9 1990.98  4988.4 1967.85  5009.8 1965.86  5010.3 1965.36  5019.1 1965.86
  5022.1 1968.11  5032.4 1971.21  5055.6 1972.72  5091.7 1971.77  5114.9 1969.87
  5138.1 1969.69  5174.2 1974.99  5187.1 1978.29  5207.7  1979.6  5238.6 1983.25
  5272.1 1985.34  5276.2 1985.36  5310.7 1985.21  5331.4 1987.74  5339.1 1990.26
  5344.3 1990.18    5352 1992.55  5362.3 1993.83  5380.3 1995.75  5403.5 1996.55
#Mann= 6 ,-1 , 0
  4879.4      .1       0  4887.4     .07       0  5009.8     .05       0
  5019.1     .07       0  5272.1      .1       0  5276.2     .07       0
Bank Sta=5009.8,5019.1
XS Rating Curve= 0 ,0
Exp/Cntr=0.3,0.1

Type RM Length L Ch R = 1 ,19566   ,469,469,469
BEGIN DESCRIPTION:
Dry Branch 34.0
END DESCRIPTION:
XS GIS Cut Line= 3
        1871975.     13974175.01        1871925.       13974275.
        1872075.     13974675.01
#Sta/Elev= 30
  4881.9 2002.32  4884.7 2002.32  4890.3 2000.47  4904.3 1997.61  4926.3 1989.01
    4935 1983.78  4940.6 1981.74    4949  1973.7  4957.4 1967.34  4962.9 1966.32
  4996.4 1964.29  5003.5  1961.8  5008.8 1961.87  5010.4 1960.52  5010.9 1960.02
  5019.8 1960.52  5025.7 1964.21  5033.7 1965.92  5039.1 1965.03  5057.8 1966.84
  5100.5 1967.47  5119.2 1969.54  5124.5 1969.07  5143.2 1970.71  5174.4 1972.15
    5210 1972.73  5320.3 1976.63  5350.6 1978.17  5388.9 1981.81  5420.9  1983.2
#Mann= 4 ,-1 , 0
  4881.9      .1       0  4926.3     .07       0  5010.4     .05       0
  5019.8     .07       0
Bank Sta=5010.4,5019.8
XS Rating Curve= 0 ,0
Exp/Cntr=0.3,0.1

Type RM Length L Ch R = 1 ,19097   ,477,477,477
BEGIN DESCRIPTION:
Dry Branch 33.0
END DESCRIPTION:
XS GIS Cut Line= 3
      1871524.99     13974075.04        1871475.       13974225.
      1871074.98     13974525.02
#Sta/Elev= 30
  4841.9 1985.37    4884 1980.31  4915.6 1974.78  4920.2 1973.13  4926.2 1970.98
  4957.8 1964.11    4974 1957.76  4974.5 1957.26  4983.8 1957.76  4989.4 1958.23
  4997.3 1960.81  5011.4  1961.8  5036.4 1962.46  5057.3 1960.49  5092.7 1959.71
  5149.1 1963.85  5178.1 1963.99  5213.5 1966.63  5228.1 1966.96  5236.4 1966.05
  5278.1 1968.38  5342.7 1980.36  5407.3 1995.83  5442.4 2001.25  5471.8 2007.05
  5478.1 2006.96  5486.4 2008.96  5492.7 2008.66  5496.8 2010.64    5500 2010.64
#Mann= 7 ,-1 , 0
  4841.9    .035       0  4920.2     .07       0    4974     .05       0
  4983.8     .07       0  5011.4    .035       0  5149.1      .1       0
  5442.4     .07       0
Bank Sta=4974,4983.8
XS Rating Curve= 0 ,0
Exp/Cntr=0.3,0.1

Type RM Length L Ch R = 1 ,18620   ,470,470,470
BEGIN DESCRIPTION:
Dry Branch 32.0
END DESCRIPTION:
XS GIS Cut Line= 3
      1871425.04     13973924.98        1871025.       13974125.
      1870924.96     13974175.02
#Sta/Elev= 30
  4558.6 1983.03    4581 1981.22  4589.4 1978.89  4625.4 1973.33  4648.1 1968.89
  4678.8 1966.37  4751.5 1965.16  4796.2 1962.12  4818.6 1959.49  4835.4 1956.11
  4849.3 1958.48  4863.3 1957.56  4871.7    1959  4894.1 1958.02  4921.1 1958.61
  4961.1 1955.61  4983.5 1952.24  4986.8 1949.76  4987.3 1949.26  4996.9 1949.76
  4997.5 1952.63  5008.7 1952.04  5014.2  1955.2  5019.8 1960.82  5036.6 1972.25
  5081.3  1996.1  5095.3 2001.42  5103.7 2003.34  5114.9 2008.38  5117.7 2008.38
#Mann= 5 ,-1 , 0
  4558.6    .035       0  4625.4     .07       0  4921.1      .1       0
  4986.8     .05       0  4996.9      .1       0
Bank Sta=4986.8,4996.9
XS Rating Curve= 0 ,0
Exp/Cntr=0.3,0.1

Type RM Length L Ch R = 1 ,18150   ,466,466,466
BEGIN DESCRIPTION:
Dry Branch 31.0
END DESCRIPTION:
XS GIS Cut Line= 3
      1871425.03     13973875.01        1871025.       13973725.
      1870875.05     13973675.02
#Sta/Elev= 30
  4568.2 1983.16  4583.4  1982.8  4624.2  1973.8  4632.3 1972.57  4638.5 1969.96
  4663.5 1966.38  4729.3 1964.37  4839.7 1958.62  4856.6 1956.71  4900.2 1956.29
  4919.8 1954.88    4942 1954.62    4950 1953.28  4955.4 1953.48  4963.4 1950.67
  4985.6 1946.18  4998.1 1946.93  5011.5 1945.98    5012 1945.48  5021.6 1945.98
  5028.9 1946.73  5058.7 1956.35  5069.2 1964.08  5079.8 1976.24  5090.3 1984.72
  5100.8 1991.19  5111.4 2001.26  5121.9 2005.07  5150.9 2018.06  5153.5 2018.06
#Mann= 5 ,-1 , 0
  4568.2    .035       0  4624.2     .07       0  5011.5     .05       0
  5021.6     .07       0  5028.9      .1       0
Bank Sta=5011.5,5021.6
XS Rating Curve= 0 ,0
Exp/Cntr=0.3,0.1

Type RM Length L Ch R = 1 ,17684   ,418,418,418
BEGIN DESCRIPTION:
Dry Branch 30.0
END DESCRIPTION:
XS GIS Cut Line= 4
      1871574.99     13973724.98        1871275.       13973375.
        1871125.       13973325.      1870970.83     13973360.18
#Sta/Elev= 30
  4539.3 1985.61    4544 1985.48  4581.5 1983.51  4631.5 1972.65  4670.1 1967.58
  4751.7 1963.65  4780.2 1961.22  4851.5 1951.92  4950.3 1949.49  4978.9 1946.49
    4997 1940.96  5026.8 1940.92  5027.3 1940.42  5036.9 1940.92  5042.4 1940.92
    5053 1960.63  5061.4 1962.74    5074 1965.96  5116.2 1981.95  5126.7 1984.91
  5155.7 1991.21  5160.9 1991.21  5177.3 1994.22  5182.4 1996.79  5219.9 1999.64
  5230.5 2001.45  5260.9 2002.41  5273.5 2003.92  5311.4  2004.1  5316.5 2005.65
#Mann= 6 ,-1 , 0
  4539.3      .1       0    4544    .035       0  4670.1     .07       0
  5026.8     .05       0  5036.9     .07       0  5061.4      .1       0
Bank Sta=5026.8,5036.9
XS Rating Curve= 0 ,0
Exp/Cntr=0.3,0.1