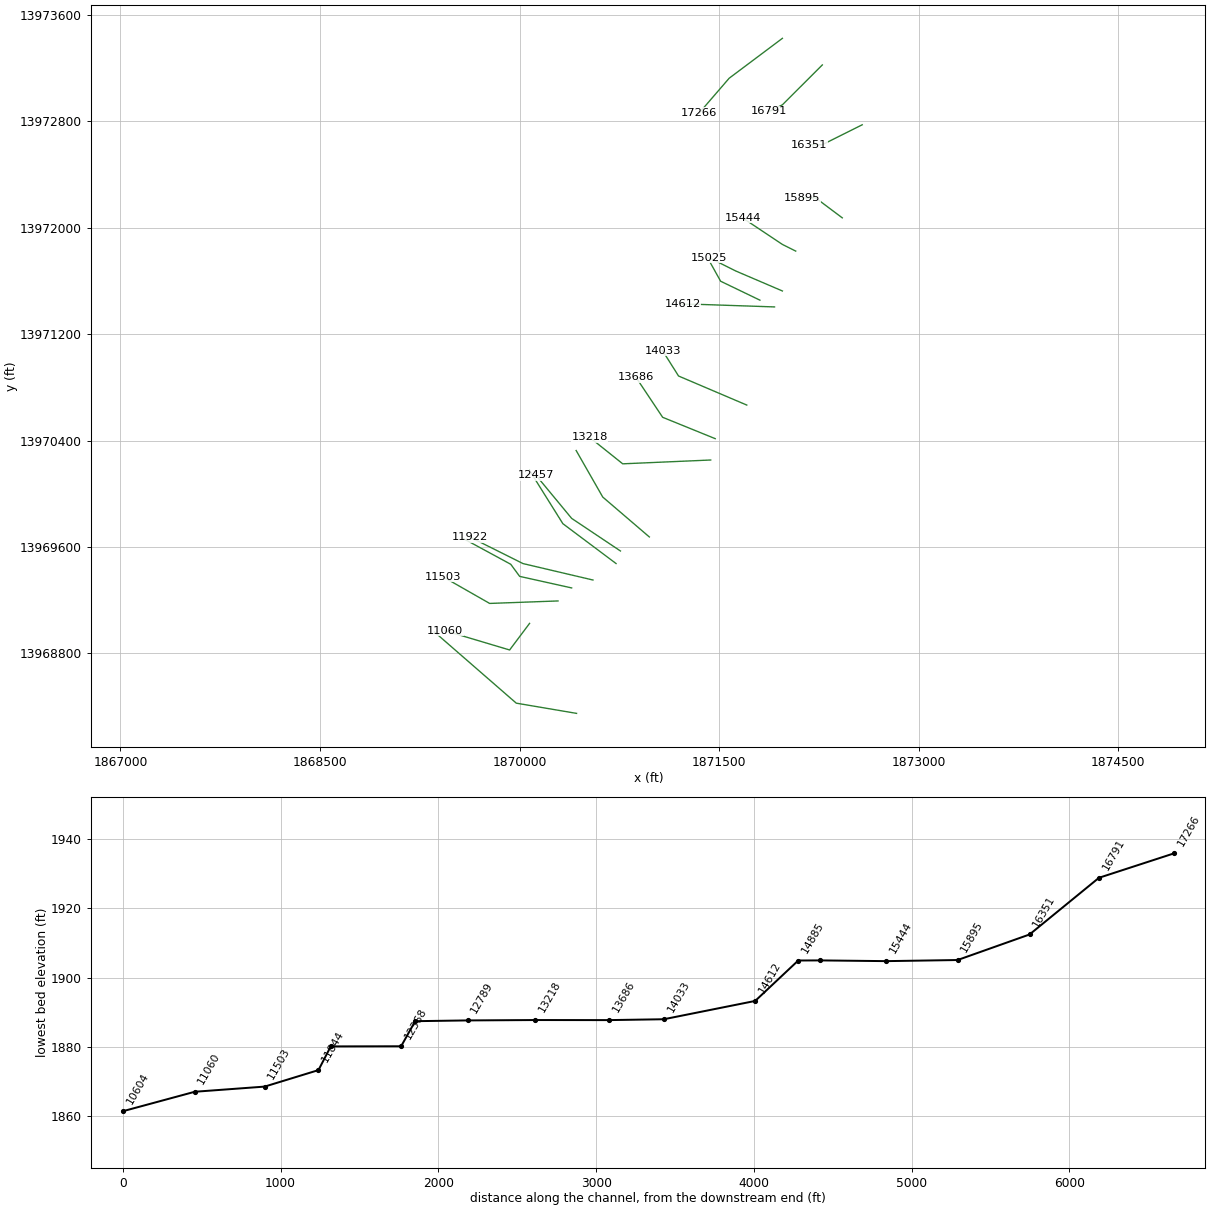
HEC-RAS study Dry Branch.prj: Dry Branch Base Level Engineering

--- Dry Branch.g01 (geometry) --- (continued)

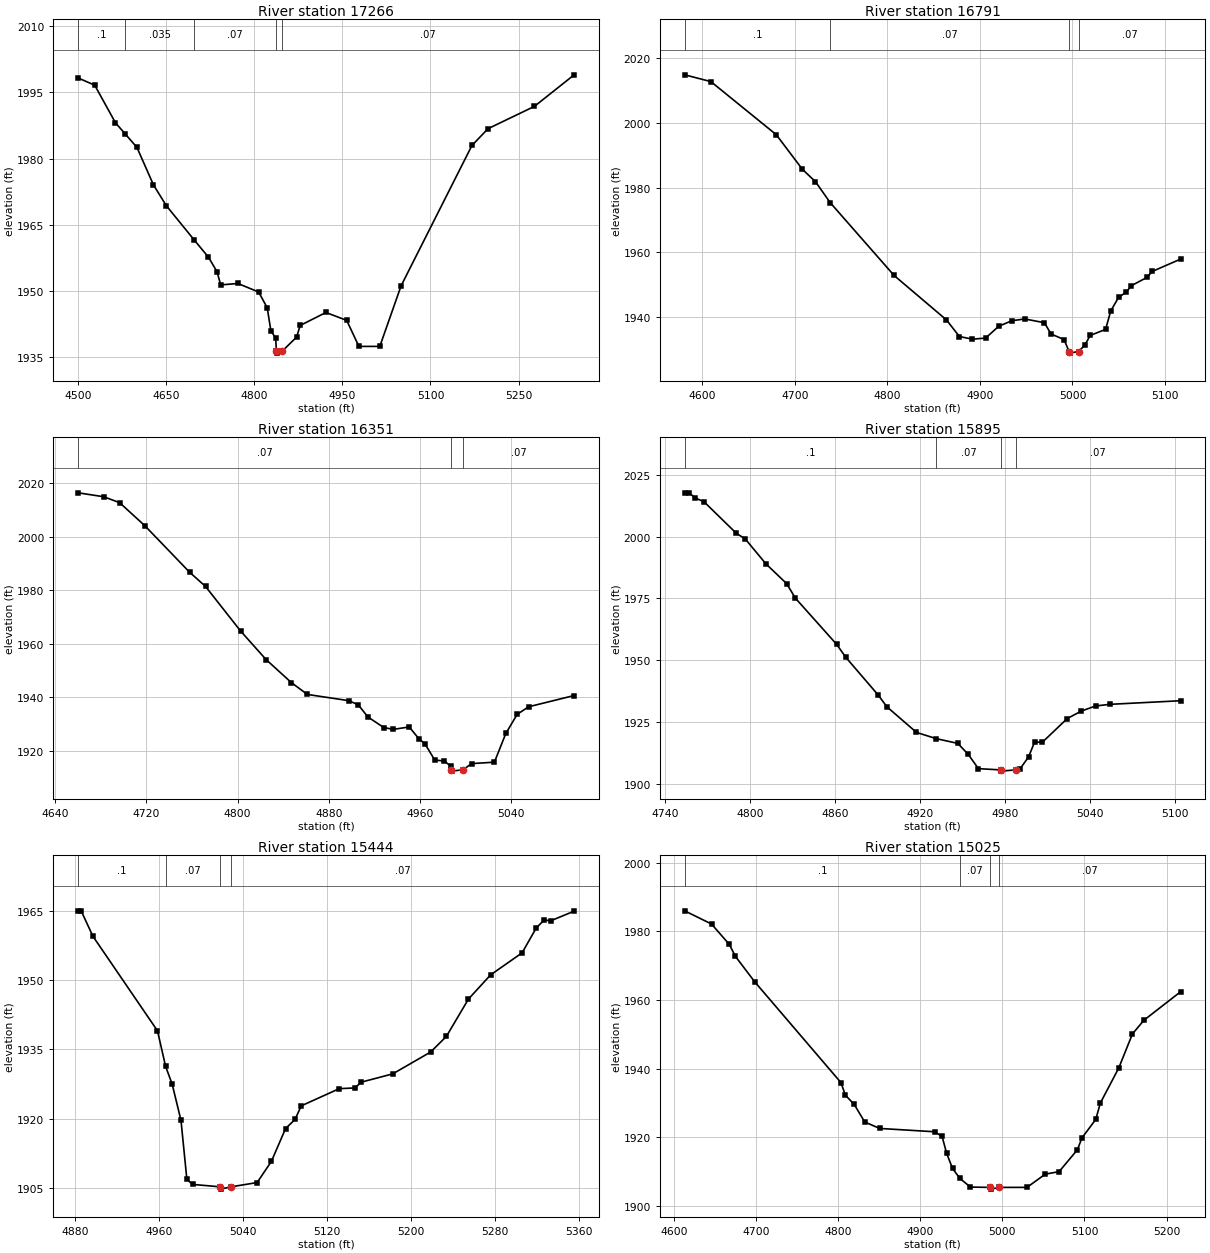
Type RM Length L Ch R = 1 ,17266   ,475,475,475
BEGIN DESCRIPTION:
Dry Branch 29.0
END DESCRIPTION:
XS GIS Cut Line= 3
      1871974.98     13973424.99        1871575.       13973125.
      1871349.87     13972863.94
#Sta/Elev= 30
    4500 1998.27  4528.1 1996.64  4563.5  1988.1  4580.1 1985.57    4600 1982.53
  4628.1 1974.04    4650 1969.31  4697.5 1961.53  4721.9 1957.61  4736.4 1954.32
  4742.7 1951.33  4771.9 1951.65  4807.3 1949.72  4821.9 1946.15  4828.1 1940.97
  4836.4 1939.22  4837.5 1936.35    4838 1935.85  4847.8 1936.35  4871.9 1939.48
  4878.1 1942.13  4921.9 1945.07  4957.3 1943.28  4978.1 1937.37  5013.7 1937.38
  5049.9 1951.11  5170.6 1982.96    5198 1986.77    5277 1991.83  5344.7 1998.99
#Mann= 5 ,-1 , 0
    4500      .1       0  4580.1    .035       0  4697.5     .07       0
  4837.5     .05       0  4847.8     .07       0
Bank Sta=4837.5,4847.8
XS Rating Curve= 0 ,0
Exp/Cntr=0.3,0.1

Type RM Length L Ch R = 1 ,16791   ,440,440,440
BEGIN DESCRIPTION:
Dry Branch 28.0
END DESCRIPTION:
XS GIS Cut Line= 3
      1872275.01     13973225.01        1871975.       13972925.
      1871874.99     13972874.99
#Sta/Elev= 30
  4580.8 2014.86  4609.1 2012.77  4679.8 1996.35  4708.1 1985.63  4722.2 1981.81
  4738.2 1975.31  4807.1 1952.84  4863.7  1939.1  4877.8 1933.94  4891.9 1933.13
  4906.1 1933.46  4920.2  1937.1  4934.4 1938.83  4948.5 1939.37  4969.7 1938.21
  4976.8 1934.73  4990.9 1933.01  4996.3 1929.31  4996.8 1928.81  5006.7 1929.31
  5013.5 1931.34  5019.1 1934.27  5035.8 1936.16  5041.4 1941.87  5049.8 1946.03
  5058.2 1947.69  5063.8 1949.69  5080.6 1952.23  5086.1 1954.05  5116.9 1957.89
#Mann= 4 ,-1 , 0
  4580.8      .1       0  4738.2     .07       0  4996.3     .05       0
  5006.7     .07       0
Bank Sta=4996.3,5006.7
XS Rating Curve= 0 ,0
Exp/Cntr=0.3,0.1

Type RM Length L Ch R = 1 ,16351   ,456,456,456
BEGIN DESCRIPTION:
Dry Branch 27.0
END DESCRIPTION:
XS GIS Cut Line= 3
      1872574.96     13972774.98        1872275.       13972625.
      1872174.96       13972625.
#Sta/Elev= 30
  4660.1 2016.51  4682.4 2015.05  4696.4 2012.85  4718.7 2004.17  4757.9 1986.82
  4771.9 1981.49  4802.6 1964.87    4825 1954.18  4847.3 1945.53  4861.3 1941.12
  4897.6  1938.8    4906 1937.24  4914.4 1932.71  4928.4 1928.74  4936.8 1928.07
  4950.7 1928.96  4959.1  1924.6  4964.7 1922.54  4973.1  1916.6  4981.5 1916.23
  4987.1 1914.34  4987.4 1912.95  4987.9 1912.45  4997.9 1912.95  5005.5 1915.26
  5025.5  1915.8  5035.5 1926.53  5045.5 1933.69  5055.5 1936.51  5095.5 1940.72
#Mann= 3 ,-1 , 0
  4660.1     .07       0  4987.4     .05       0  4997.9     .07       0
Bank Sta=4987.4,4997.9
XS Rating Curve= 0 ,0
Exp/Cntr=0.3,0.1

Type RM Length L Ch R = 1 ,15895   ,451,451,451
BEGIN DESCRIPTION:
Dry Branch 26.0
END DESCRIPTION:
XS GIS Cut Line= 3
      1872425.02     13972074.98        1872225.       13972225.
      1872125.03       13972225.
#Sta/Elev= 30
  4754.1 2017.79  4757.3 2017.79  4761.4 2015.74  4767.7  2014.2  4790.6 2001.37
  4796.8 1999.15  4811.4 1989.05    4826 1981.05  4832.3 1975.08  4861.4 1956.39
  4867.7 1951.25  4890.6 1935.94  4896.8 1931.14  4917.7 1920.76  4931.6 1918.24
  4946.8 1916.32  4954.1 1911.96  4961.4 1906.08    4977 1905.58  4977.5 1905.08
  4987.6 1905.58  4990.6 1905.86  4996.8 1910.83    5001 1916.82  5006.6 1916.82
  5024.1 1926.38  5034.1 1929.42  5044.1 1931.47  5054.1 1932.13  5104.1 1933.59
#Mann= 4 ,-1 , 0
  4754.1      .1       0  4931.6     .07       0    4977     .05       0
  4987.6     .07       0
Bank Sta=4977,4987.6
XS Rating Curve= 0 ,0
Exp/Cntr=0.3,0.1

Type RM Length L Ch R = 1 ,15444   ,419,419,419
BEGIN DESCRIPTION:
Dry Branch 25.0
END DESCRIPTION:
XS GIS Cut Line= 3
      1872075.03     13971824.98        1871975.       13971875.
        1871675.       13972075.
#Sta/Elev= 30
  4882.7 1964.96  4885.5 1964.96  4896.7 1959.46  4958.2 1939.01  4965.9 1931.35
  4972.2 1927.46  4980.6 1919.62  4986.2 1906.87  4991.7 1905.78  5017.8 1905.26
  5018.3 1904.76  5028.4 1905.26  5053.1 1906.18  5066.7 1910.75  5080.2 1917.86
  5089.2 1919.83  5095.2 1922.78  5131.3 1926.49  5146.3 1926.65  5152.3  1927.9
  5182.3 1929.69  5218.4 1934.42  5233.4 1937.79  5254.4 1945.87  5275.5  1951.1
  5305.5 1955.87    5319 1961.25  5326.6 1962.99  5332.6 1962.79  5355.1 1964.89
#Mann= 4 ,-1 , 0
  4882.7      .1       0  4965.9     .07       0  5017.8     .05       0
  5028.4     .07       0
Bank Sta=5017.8,5028.4
XS Rating Curve= 0 ,0
Exp/Cntr=0.3,0.1

Type RM Length L Ch R = 1 ,15025   ,140,140,140
BEGIN DESCRIPTION:
Dry Branch 24.0
END DESCRIPTION:
XS GIS Cut Line= 3
      1871975.03     13971524.99        1871625.       13971675.
      1871425.02     13971774.99
#Sta/Elev= 30
  4612.8 1985.95  4645.5 1982.11  4667.2 1976.18  4674.5 1972.74  4698.1 1965.31
  4803.2 1935.98  4808.7 1932.29  4819.5  1929.6  4832.2 1924.51  4850.4 1922.63
  4917.5 1921.66  4926.5 1920.31    4932 1915.42  4939.2 1910.99  4948.2  1908.1
    4961 1905.57  4985.5 1905.47    4986 1904.97  4996.2 1905.47    5030 1905.48
  5052.3 1909.34  5069.1 1910.05  5091.4 1916.43    5097 1919.89  5113.8 1925.26
  5119.4 1930.04  5141.8 1940.21  5158.5 1950.14  5172.5 1954.12  5217.2 1962.41
#Mann= 4 ,-1 , 0
  4612.8      .1       0  4948.2     .07       0  4985.5     .05       0
  4996.2     .07       0
Bank Sta=4985.5,4996.2
XS Rating Curve= 0 ,0
Exp/Cntr=0.3,0.1

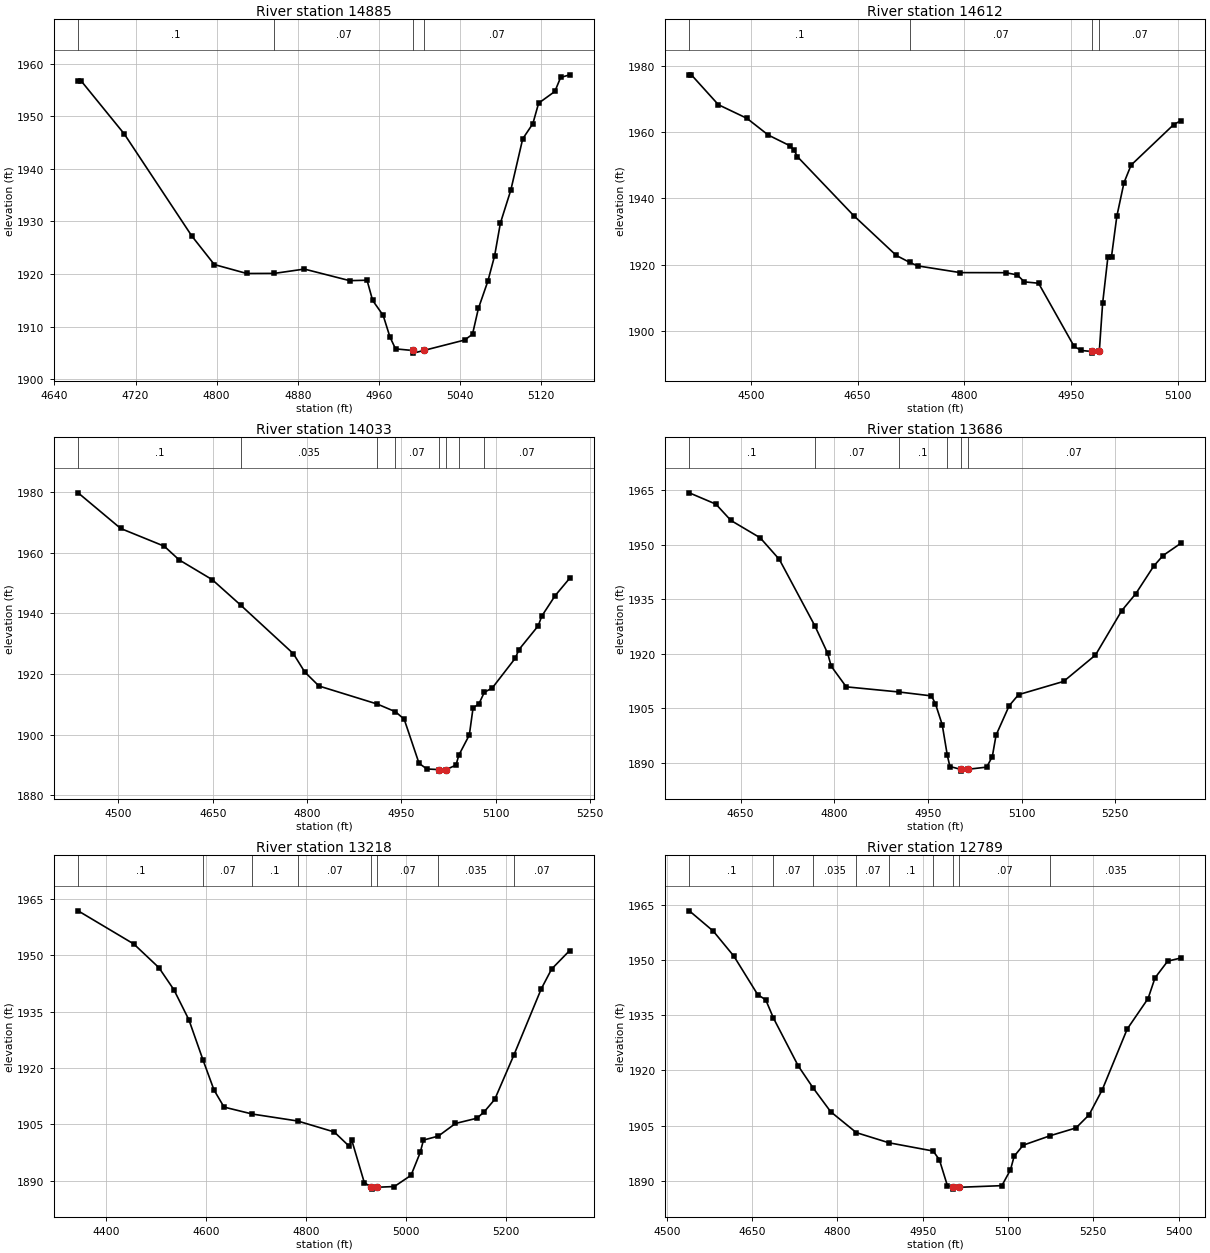
Type RM Length L Ch R = 1 ,14885   ,273,273,273
BEGIN DESCRIPTION:
Dry Branch 23.1
END DESCRIPTION:
XS GIS Cut Line= 3
      1871805.96     13971455.93      1871510.83     13971598.29
      1871434.42     13971735.48
#Sta/Elev= 30
  4663.4 1956.62  4666.7 1956.62  4708.9 1946.61  4775.5 1927.21  4797.7 1921.78
  4829.7 1920.08  4856.9  1920.1  4886.5 1920.92  4931.2 1918.72  4948.3  1918.8
  4953.8 1914.97  4964.2 1912.12  4970.9    1908  4976.4 1905.75  4993.4 1905.44
  4993.9 1904.94  5004.1 1905.44  5044.5 1907.43  5052.3 1908.53  5058.1 1913.43
  5067.4  1918.6  5074.1 1923.44  5079.8 1929.66  5090.1 1935.95  5101.8 1945.68
  5111.8 1948.56  5117.5 1952.46  5133.5 1954.69  5139.2 1957.35  5148.1 1957.85
#Mann= 4 ,-1 , 0
  4663.4      .1       0  4856.9     .07       0  4993.4     .05       0
  5004.1     .07       0
Bank Sta=4993.4,5004.1
XS Rating Curve= 0 ,0
Exp/Cntr=0.3,0.1

Type RM Length L Ch R = 1 ,14612   ,579,579,579
BEGIN DESCRIPTION:
Dry Branch 23.0
END DESCRIPTION:
XS GIS Cut Line= 3
      1871915.92     13971404.98        1871325.       13971425.
      1871224.96       13971425.
#Sta/Elev= 30
  4413.2 1977.37  4416.1 1977.37  4454.1 1968.34  4494.2 1964.23  4524.2 1959.18
  4554.2 1955.99  4560.3 1954.69  4565.3 1952.63  4644.3 1934.85  4704.3 1922.79
  4723.4 1920.67  4734.3 1919.64  4794.3  1917.6  4858.1 1917.58  4874.4 1916.91
  4884.4 1914.81  4904.4 1914.39  4954.4 1895.31  4964.4 1894.07  4979.1 1893.77
  4979.6 1893.27  4989.8 1893.77  4994.5 1908.31    5002 1922.45    5007 1922.45
  5014.5 1934.65  5024.5 1944.74  5034.5 1950.08  5094.5 1962.34  5104.5 1963.51
#Mann= 4 ,-1 , 0
  4413.2      .1       0  4723.4     .07       0  4979.1     .05       0
  4989.8     .07       0
Bank Sta=4979.1,4989.8
XS Rating Curve= 0 ,0
Exp/Cntr=0.3,0.1

Type RM Length L Ch R = 1 ,14033   ,347,347,347
BEGIN DESCRIPTION:
Dry Branch 22.0
END DESCRIPTION:
XS GIS Cut Line= 3
      1871707.29     13970666.91       1871194.6     13970885.43
      1871074.98     13971075.04
#Sta/Elev= 30
    4436 1979.79  4503.7 1968.03  4572.9 1962.19  4596.5 1957.69  4649.2 1951.15
  4694.2  1942.8  4778.2 1926.73  4796.4 1920.67  4818.9 1916.07  4911.6 1910.12
  4940.6 1907.57  4954.4 1905.12    4978 1890.58  4990.4  1888.7  5009.9 1888.49
  5010.4 1887.99  5021.3 1888.49  5036.8    1890  5041.3 1893.25    5058 1899.92
  5063.9 1908.82  5073.3 1910.21  5081.8 1913.99  5094.5 1915.43    5131 1925.23
  5136.9 1928.08  5167.4 1935.89  5173.3 1939.17  5194.5 1945.89  5217.5  1951.6
#Mann= 8 ,-1 , 0
    4436      .1       0  4694.2    .035       0  4911.6      .1       0
  4940.6     .07       0  5009.9     .05       0  5021.3     .07       0
  5041.3      .1       0  5081.8     .07       0
Bank Sta=5009.9,5021.3
XS Rating Curve= 0 ,0
Exp/Cntr=0.3,0.1

Type RM Length L Ch R = 1 ,13686   ,468,468,468
BEGIN DESCRIPTION:
Dry Branch 21.0
END DESCRIPTION:
XS GIS Cut Line= 3
      1871470.14     13970414.26        1871075.       13970575.
      1870875.02     13970874.96
#Sta/Elev= 30
    4568 1964.24  4610.6 1961.13  4634.6 1956.65  4681.5 1951.88  4712.2 1945.93
    4769  1927.7  4789.5 1920.15  4795.2 1916.59  4819.3 1910.91    4904 1909.49
  4955.8 1908.42  4962.2 1906.22    4973  1900.5  4981.2 1892.04  4985.3 1889.01
  5002.4 1888.24  5002.9 1887.74  5013.8 1888.24  5044.2 1888.84  5053.2 1891.73
  5059.2 1897.62  5080.2 1905.71  5095.2 1908.76  5167.4  1912.4  5218.4 1919.65
  5260.5 1931.86    5283 1936.52  5311.6 1944.08  5326.6    1947  5355.1 1950.37
#Mann= 6 ,-1 , 0
    4568      .1       0    4769     .07       0    4904      .1       0
  4981.2     .07       0  5002.4     .05       0  5013.8     .07       0
Bank Sta=5002.4,5013.8
XS Rating Curve= 0 ,0
Exp/Cntr=0.3,0.1

Type RM Length L Ch R = 1 ,13218   ,429,429,429
BEGIN DESCRIPTION:
Dry Branch 20.0
END DESCRIPTION:
XS GIS Cut Line= 3
      1871436.23     13970253.69        1870775.       13970225.
      1870525.01     13970424.99
#Sta/Elev= 30
  4344.8 1961.81  4456.1 1952.98  4506.2 1946.69  4536.2  1940.8  4566.2 1932.79
  4594.5 1922.05  4616.3 1914.13  4636.3 1909.59  4693.1 1907.73  4783.3 1905.89
  4856.5 1902.97  4886.4 1899.16  4891.4 1900.82  4916.6 1889.47  4930.7 1888.26
  4931.2 1887.76  4942.4 1888.26  4976.6 1888.45  5009.9 1891.44  5028.3 1897.52
  5034.7 1900.81  5064.4 1901.87  5098.7 1905.23  5141.9 1906.64  5156.3 1908.37
  5177.1 1911.63  5215.7 1923.54    5270 1941.03  5290.8 1946.32  5326.8 1951.24
#Mann= 8 ,-1 , 0
  4344.8      .1       0  4594.5     .07       0  4693.1      .1       0
  4783.3     .07       0  4930.7     .05       0  4942.4     .07       0
  5064.4    .035       0  5215.7     .07       0
Bank Sta=4930.7,4942.4
XS Rating Curve= 0 ,0
Exp/Cntr=0.3,0.1

Type RM Length L Ch R = 1 ,12789   ,332,332,332
BEGIN DESCRIPTION:
Dry Branch 19.0
END DESCRIPTION:
XS GIS Cut Line= 3
      1870974.99     13969675.01        1870625.       13969975.
      1870424.99     13970325.02
#Sta/Elev= 30
  4539.7 1963.54  4581.9    1958  4618.2 1951.15  4659.9  1940.7  4674.1 1939.26
  4687.6  1934.3  4731.2 1921.25  4757.1  1915.3  4788.3 1908.75  4833.3 1903.06
  4890.6 1900.29  4968.3 1898.04  4979.3 1895.68  4993.5 1888.56  5002.6 1888.15
  5003.1 1887.65  5014.5 1888.15  5089.2  1888.6  5104.3 1892.91  5110.8 1896.62
  5126.6 1899.63  5174.6 1902.24  5219.5 1904.34  5242.5 1907.91  5265.6 1914.72
  5309.5  1931.3  5346.2 1939.62  5358.4 1945.26  5380.7 1949.82  5403.8 1950.68
#Mann= 9 ,-1 , 0
  4539.7      .1       0  4687.6     .07       0  4757.1    .035       0
  4833.3     .07       0  4890.6      .1       0  4968.3     .07       0
  5002.6     .05       0  5014.5     .07       0  5174.6    .035       0
Bank Sta=5002.6,5014.5
XS Rating Curve= 0 ,0
Exp/Cntr=0.3,0.1

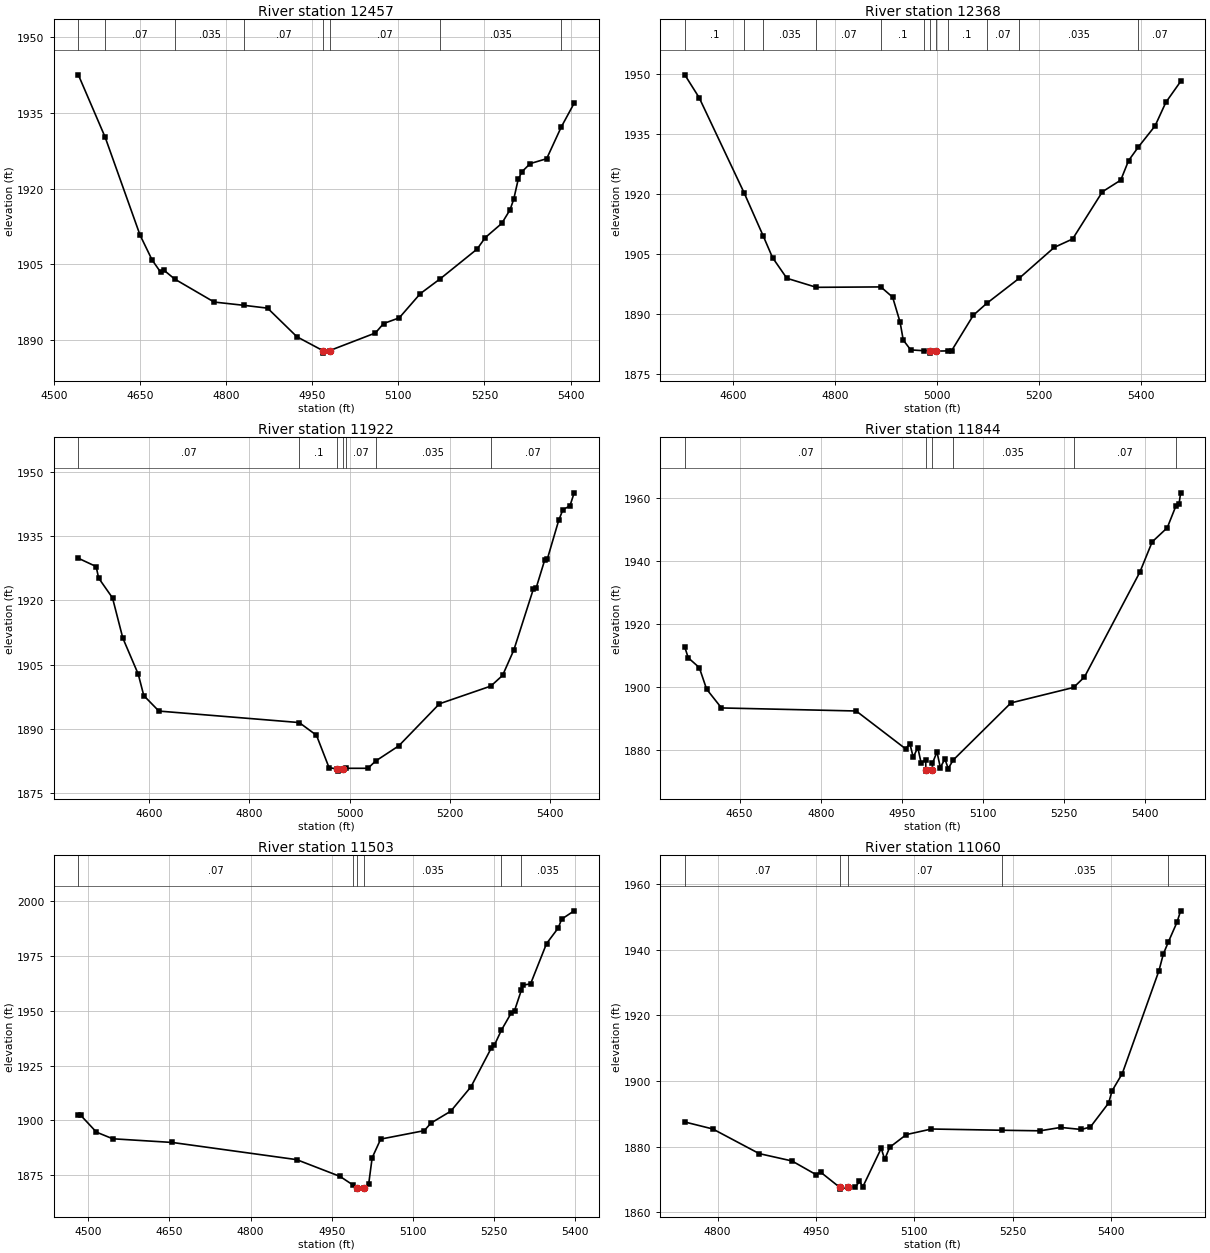
Type RM Length L Ch R = 1 ,12457   ,89,89,89
BEGIN DESCRIPTION:
Dry Branch 18.1
END DESCRIPTION:
XS GIS Cut Line= 3
      1870757.97     13969569.41      1870391.18     13969814.66
      1870122.13     13970140.12
#Sta/Elev= 30
  4542.8 1942.57  4589.5 1930.21  4650.2 1910.84  4671.2  1905.9  4686.3 1903.44
  4692.3 1903.82  4710.7  1902.1  4779.3 1897.55    4832 1896.89  4872.4 1896.34
  4923.5 1890.67  4968.6 1887.93  4969.1 1887.43  4980.5 1887.93  5060.1 1891.42
  5074.4 1893.29  5101.7 1894.42  5138.3 1899.21  5173.5  1902.2  5237.2 1908.04
  5251.6 1910.33  5280.2 1913.13  5294.6 1915.82  5301.1 1917.94  5308.8 1921.84
  5315.4 1923.37  5329.7 1924.98  5358.4 1925.95  5383.7  1932.2  5406.3 1936.95
#Mann= 8 ,-1 , 0
  4542.8      .1       0  4589.5     .07       0  4710.7    .035       0
    4832     .07       0  4968.6     .05       0  4980.5     .07       0
  5173.5    .035       0  5383.7     .07       0
Bank Sta=4968.6,4980.5
XS Rating Curve= 0 ,0
Exp/Cntr=0.3,0.1

Type RM Length L Ch R = 1 ,12368   ,446,446,446
BEGIN DESCRIPTION:
Dry Branch 18.0
END DESCRIPTION:
XS GIS Cut Line= 3
      1870725.01     13969474.99        1870325.       13969775.
      1870075.01     13970174.99
#Sta/Elev= 30
  4505.8 1949.76  4533.9 1944.06  4622.1 1920.25  4659.8 1909.39  4677.7 1904.08
  4705.8  1898.9  4763.7 1896.64    4890 1896.74  4913.1 1894.18  4927.7 1887.94
  4933.9 1883.46  4948.5    1881  4974.1 1880.79  4986.3 1880.69  4986.8 1880.19
  4998.3 1880.69  5020.7 1880.75  5028.8 1880.82  5071.3 1889.67  5097.3 1892.61
  5161.2 1898.91  5229.9 1906.63  5265.8 1908.72  5324.2 1920.53  5360.2 1923.44
  5375.5 1928.32  5394.5 1931.69  5427.4 1936.99  5448.6 1942.89  5477.5  1948.1
#Mann= 12 ,-1 , 0
  4505.8      .1       0  4622.1     .07       0  4659.8    .035       0
  4763.7     .07       0    4890      .1       0  4974.1     .07       0
  4986.3     .05       0  4998.3     .07       0  5020.7      .1       0
  5097.3     .07       0  5161.2    .035       0  5394.5     .07       0
Bank Sta=4986.3,4998.3
XS Rating Curve= 0 ,0
Exp/Cntr=0.3,0.1

Type RM Length L Ch R = 1 ,11922   ,78,78,78
BEGIN DESCRIPTION:
Dry Branch 17.0
END DESCRIPTION:
XS GIS Cut Line= 3
      1870551.26     13969351.13        1870025.       13969475.
      1869624.96     13969675.02
#Sta/Elev= 30
  4459.4 1929.81  4494.8 1927.88  4499.9 1925.18  4527.5 1920.56    4548  1911.2
  4578.8 1902.76  4589.8 1897.77  4619.9 1894.16  4899.5 1891.48  4933.9 1888.51
  4958.9 1880.97  4975.4 1880.65  4975.9 1880.15  4987.4 1880.65  4992.1 1880.81
  5036.4 1880.81  5051.7  1882.5  5097.9 1886.05  5178.9 1895.86  5281.3 1899.99
  5304.7 1902.48  5327.1  1908.4  5366.2 1922.69  5371.8 1922.97  5388.6 1929.38
  5394.1 1929.73  5416.5 1938.64  5424.9 1941.14  5438.9 1942.02  5447.3 1945.07
#Mann= 7 ,-1 , 0
  4459.4     .07       0  4899.5      .1       0  4975.4     .05       0
  4987.4      .1       0  4992.1     .07       0  5051.7    .035       0
  5281.3     .07       0
Bank Sta=4975.4,4987.4
XS Rating Curve= 0 ,0
Exp/Cntr=0.3,0.1

Type RM Length L Ch R = 1 ,11844   ,341,341,341
BEGIN DESCRIPTION:
Dry Branch 16.1
END DESCRIPTION:
XS GIS Cut Line= 4
      1870391.14     13969291.66      1870000.55     13969378.46
      1869933.28      13969469.6      1869578.73     13969662.01
#Sta/Elev= 30
  4548.6 1912.67  4554.9  1909.3  4575.4 1906.18  4588.9 1899.34  4616.4 1893.37
  4865.5  1892.4  4956.8  1880.4  4964.8 1881.98    4971 1877.71  4979.4  1880.8
  4985.6 1875.88    4994 1876.95  4994.3 1873.81  4994.8 1873.31  5006.3 1873.81
  5006.6 1875.86  5014.9 1879.39  5021.1 1874.45  5029.5 1877.17  5035.7 1874.13
  5044.9 1876.83  5151.7 1894.97  5267.5 1899.87  5287.6 1903.19    5390 1936.47
  5412.8 1946.09  5440.7 1950.58  5456.3 1957.33  5462.6 1958.27  5465.4 1961.66
#Mann= 6 ,-1 , 0
  4548.6     .07       0  4994.3     .05       0  5006.3     .07       0
  5044.9    .035       0  5267.5     .07       0  5456.3    .035       0
Bank Sta=4994.3,5006.3
XS Rating Curve= 0 ,0
Exp/Cntr=0.3,0.1

Type RM Length L Ch R = 1 ,11503   ,443,443,443
BEGIN DESCRIPTION:
Dry Branch 16.0
END DESCRIPTION:
XS GIS Cut Line= 3
      1870288.52     13969193.72        1869775.       13969175.
      1869424.98     13969375.01
#Sta/Elev= 30
  4481.5  1902.3  4485.8  1902.3    4515 1894.58  4545.1 1891.55  4655.1 1889.87
  4885.3 1882.02  4965.3 1874.38  4989.2 1870.48  4997.2 1869.05  4997.7 1868.55
  5009.3 1869.05  5018.4 1870.73  5024.9 1882.86  5040.7  1891.4  5121.3 1895.26
  5133.6 1898.71  5170.3 1904.15  5207.7 1915.31  5245.1 1932.93  5250.9 1934.28
  5263.9 1941.15  5282.6 1949.21  5288.3 1950.11  5301.1 1959.63  5304.2 1961.74
  5317.9 1962.31  5347.4  1980.7    5369 1987.82  5375.4 1991.88  5398.5 1995.67
#Mann= 6 ,-1 , 0
  4481.5     .07       0  4989.2    .035       0  4997.2    .035       0
  5009.3    .035       0  5263.9     .07       0  5301.1    .035       0
Bank Sta=4997.2,5009.3
XS Rating Curve= 0 ,0
Exp/Cntr=0.3,0.1

Type RM Length L Ch R = 1 ,11060   ,456,456,456
BEGIN DESCRIPTION:
Dry Branch 15.0
END DESCRIPTION:
XS GIS Cut Line= 3
      1870074.98     13969024.97        1869925.       13968825.
      1869439.74     13968969.93
#Sta/Elev= 30
    4750 1887.53  4792.7  1885.4  4863.5 1877.89  4913.5 1875.65    4950 1871.51
  4957.3 1872.22  4986.6 1867.56  4987.1 1867.06  4998.7 1867.56  5010.4 1867.71
  5016.5 1869.41  5021.7 1867.81  5049.7 1879.52  5054.9 1876.11  5062.6 1879.82
    5088 1883.69  5126.3 1885.39  5233.6 1885.01    5292 1884.84  5323.5 1885.87
  5354.8 1885.25  5368.7 1885.99  5396.6 1893.32  5401.8 1897.02  5417.4  1902.3
  5473.3 1933.63    5480 1938.73  5487.8 1942.47  5500.9 1948.44  5506.4 1951.91
#Mann= 5 ,-1 , 0
    4750     .07       0  4986.6     .05       0  4998.7     .07       0
  5233.6    .035       0  5487.8      .1       0
Bank Sta=4986.6,4998.7
XS Rating Curve= 0 ,0
Exp/Cntr=0.3,0.1

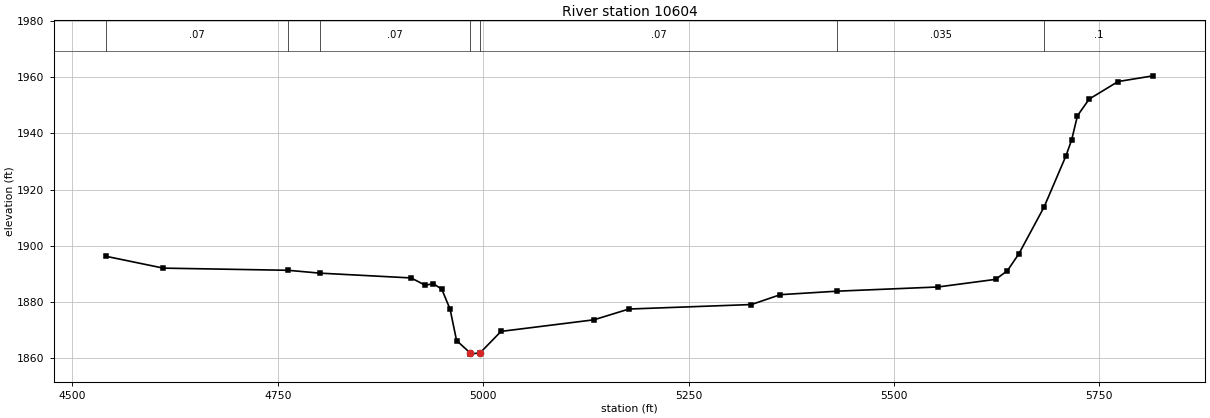
Type RM Length L Ch R = 1 ,10604   ,469,469,469
BEGIN DESCRIPTION:
Dry Branch 14.0
END DESCRIPTION:
XS GIS Cut Line= 3
      1870428.05     13968348.18        1869975.       13968425.
      1869360.27     13968960.07
#Sta/Elev= 30
  4540.8 1896.27  4610.7 1892.05  4762.5 1891.28    4801 1890.27  4912.3 1888.56
  4929.3 1885.99  4939.5 1886.48  4949.6 1884.56  4959.7 1877.44  4967.6 1866.27
  4983.9 1861.94  4984.4 1861.44  4996.4 1861.94  5021.7 1869.53  5134.7 1873.65
  5177.4 1877.49  5326.5 1879.09  5361.6  1882.6    5431 1883.85  5553.4 1885.34
  5623.6 1888.05  5637.9 1891.08  5652.1  1897.2  5682.7 1913.83  5709.1 1931.88
  5716.2 1937.67  5723.3 1946.31  5737.6 1952.23  5772.7 1958.46  5815.3  1960.5
#Mann= 7 ,-1 , 0
  4540.8     .07       0  4762.5    .035       0    4801     .07       0
  4983.9     .05       0  4996.4     .07       0    5431    .035       0
  5682.7      .1       0
Bank Sta=4983.9,4996.4
XS Rating Curve= 0 ,0
Exp/Cntr=0.3,0.1