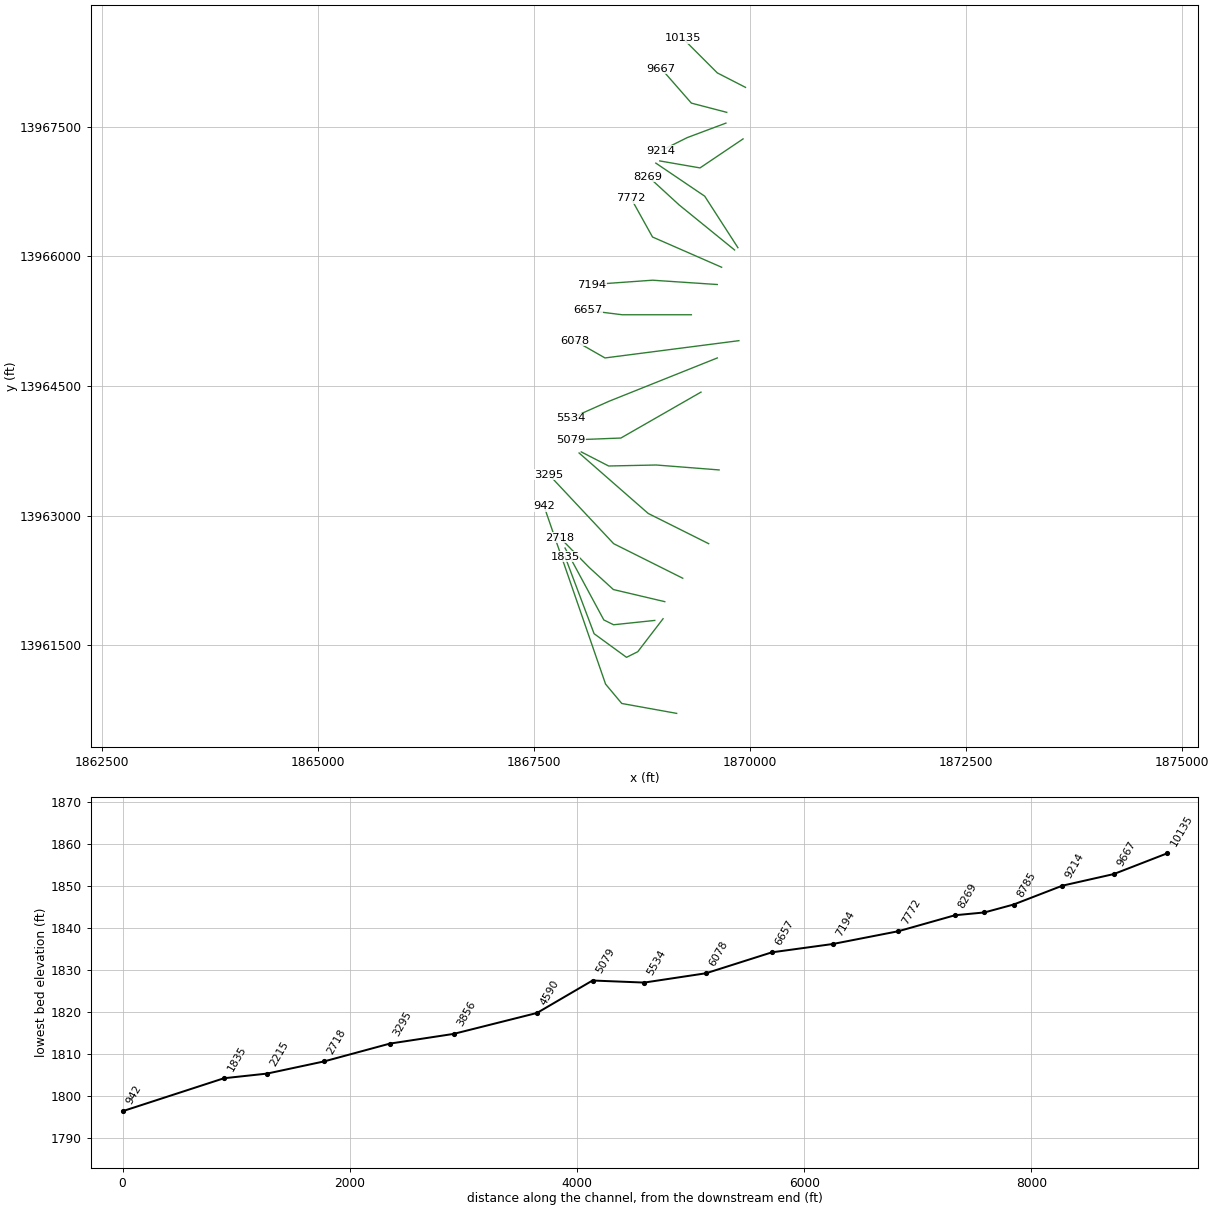
HEC-RAS study Dry Branch.prj: Dry Branch Base Level Engineering

--- Dry Branch.g01 (geometry) --- (continued)

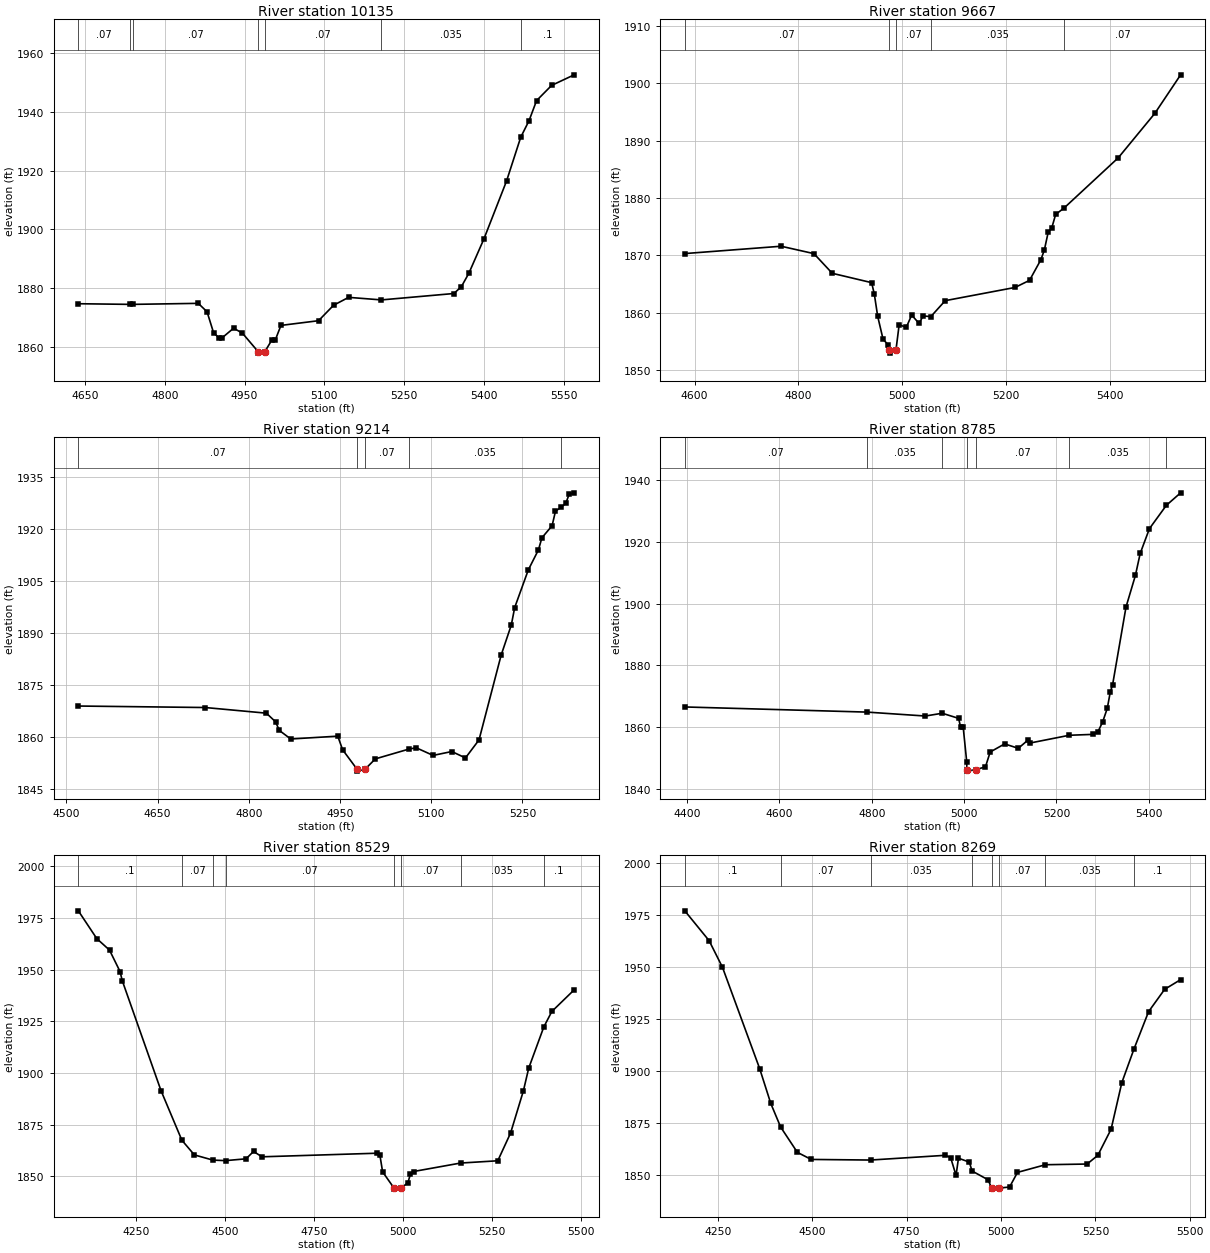
Type RM Length L Ch R = 1 ,10135   ,468,468,468
BEGIN DESCRIPTION:
Dry Branch 13.0
END DESCRIPTION:
XS GIS Cut Line= 3
       1869951.4     13967957.33        1869625.       13968125.
      1869225.02     13968524.98
#Sta/Elev= 30
  4637.4 1874.68  4734.9 1874.46  4739.5 1874.46    4863 1874.81  4879.5 1871.94
  4891.9 1864.73  4901.7 1863.14  4907.3 1862.99  4929.5 1866.36  4946.1 1864.64
  4975.6 1858.36  4976.1 1857.86  4988.2 1858.36  5001.5 1862.35  5007.9 1862.35
  5018.5  1867.3  5089.2  1868.9  5117.5 1874.16  5145.8 1876.85  5207.5 1875.98
  5343.8 1878.16  5357.9  1880.5    5372 1885.08  5400.3 1896.76  5442.8 1916.45
  5469.5 1931.36  5485.2 1937.04  5499.3 1943.84  5527.6 1949.02    5570 1952.62
#Mann= 7 ,-1 , 0
  4637.4     .07       0  4734.9    .035       0  4739.5     .07       0
  4975.6     .05       0  4988.2     .07       0  5207.5    .035       0
  5469.5      .1       0
Bank Sta=4975.6,4988.2
XS Rating Curve= 0 ,0
Exp/Cntr=0.3,0.1

Type RM Length L Ch R = 1 ,9667    ,453,453,453
BEGIN DESCRIPTION:
Dry Branch 12.0
END DESCRIPTION:
XS GIS Cut Line= 3
      1869734.41     13967668.36        1869325.       13967775.
      1868974.99     13968175.01
#Sta/Elev= 30
  4581.3  1870.3  4766.7 1871.58  4829.9 1870.29  4865.2 1866.86    4941 1865.23
  4946.2 1863.22  4952.7 1859.34    4963 1855.37  4973.4 1854.32  4975.2 1853.44
  4975.7 1852.94  4987.8 1853.44    4994  1857.9  5007.7 1857.43  5018.1 1859.58
  5032.4 1858.11    5040 1859.42    5055 1859.31  5082.7 1862.09    5217 1864.39
    5245 1865.63  5266.8 1869.22  5273.5 1870.91    5281 1874.05  5287.7 1874.74
  5295.3 1877.13  5311.6 1878.25  5415.8    1887  5486.1 1894.73  5535.9 1901.47
#Mann= 5 ,-1 , 0
  4581.3     .07       0  4975.2     .05       0  4987.8     .07       0
    5055    .035       0  5311.6     .07       0
Bank Sta=4975.2,4987.8
XS Rating Curve= 0 ,0
Exp/Cntr=0.3,0.1

Type RM Length L Ch R = 1 ,9214    ,429,429,429
BEGIN DESCRIPTION:
Dry Branch 11.0
END DESCRIPTION:
XS GIS Cut Line= 3
       1869724.6     13967543.46        1869275.       13967375.
      1868975.03     13967225.02
#Sta/Elev= 30
  4519.5 1868.93  4728.1  1868.5  4828.8 1866.87  4843.8  1864.4  4850.1  1861.9
  4868.8 1859.43  4946.2 1860.25  4954.2 1856.32  4978.1 1850.67  4978.6 1850.17
  4990.8 1850.67    5008  1853.7  5062.6 1856.49  5075.1 1856.91    5103  1854.7
  5133.8 1855.82  5156.2 1853.97  5178.5 1859.16  5214.9 1883.59  5231.6 1892.27
  5237.2 1897.31  5259.6 1908.17  5276.3 1913.95  5281.9  1917.4  5298.7 1920.89
  5304.3  1925.1  5313.4 1926.18  5321.1 1927.32  5326.7 1929.91    5335 1930.37
#Mann= 5 ,-1 , 0
  4519.5     .07       0  4978.1     .05       0  4990.8     .07       0
  5062.6    .035       0  5313.4      .1       0
Bank Sta=4978.1,4990.8
XS Rating Curve= 0 ,0
Exp/Cntr=0.3,0.1

Type RM Length L Ch R = 1 ,8785    ,256,256,256
BEGIN DESCRIPTION:
Dry Branch 10.0
END DESCRIPTION:
XS GIS Cut Line= 3
      1869923.18     13967360.63        1869425.       13967025.
      1868958.43     13967105.78
#Sta/Elev= 30
  4394.9 1866.49  4789.9 1864.82  4916.1 1863.55  4952.6 1864.45  4988.1 1862.79
  4992.6 1859.84  4998.1 1859.84  5005.7 1848.67    5006 1846.18  5006.5 1845.68
  5025.7 1846.18  5046.3 1847.07  5056.5 1851.88  5087.8 1854.51  5117.4 1853.08
  5137.4 1855.62  5142.4 1854.78  5227.9 1857.31  5279.8  1857.6  5289.9 1858.42
  5300.1 1861.62  5310.2 1866.04  5316.6 1871.26  5321.7 1873.67  5350.8 1898.91
  5371.1 1909.13  5381.5 1916.27  5401.5 1924.31  5438.2 1931.88  5469.1 1935.93
#Mann= 7 ,-1 , 0
  4394.9     .07       0  4789.9    .035       0  4952.6     .07       0
    5006     .05       0  5025.7     .07       0  5227.9    .035       0
  5438.2      .1       0
Bank Sta=5006,5025.7
XS Rating Curve= 0 ,0
Exp/Cntr=0.3,0.1

Type RM Length L Ch R = 1 ,8529    ,260,260,260
BEGIN DESCRIPTION:
Mapping XS 0d18dace
END DESCRIPTION:
XS GIS Cut Line= 3
      1869863.69      13966101.4      1869479.15      13966697.8
      1868913.04     13967080.77
#Sta/Elev= 30
  4087.9 1978.39  4139.8 1964.95  4175.5  1959.4  4205.2 1948.99  4211.3 1944.62
  4320.2 1891.43  4378.8 1867.45  4413.9 1860.35    4466 1857.84  4501.4 1857.58
  4559.1 1858.46  4580.2 1862.03  4603.8 1859.43  4927.8 1861.17  4935.3 1860.15
  4942.8 1852.15  4974.9  1844.3  4975.4  1843.8  4994.6  1844.3  5013.8 1846.89
  5020.7 1850.88  5029.7 1852.32  5161.7 1856.41  5266.4 1857.51  5302.4 1870.94
  5338.3 1891.29  5353.3  1902.3  5395.7 1922.22  5418.3 1929.72    5481 1940.17
#Mann= 8 ,-1 , 0
  4087.9      .1       0  4378.8     .07       0    4466    .035       0
  4501.4     .07       0  4974.9     .05       0  4994.6     .07       0
  5161.7    .035       0  5395.7      .1       0
Bank Sta=4974.9,4994.6
XS Rating Curve= 0 ,0
Exp/Cntr=0.3,0.1

Type RM Length L Ch R = 1 ,8269    ,497,497,497
BEGIN DESCRIPTION:
Dry Branch 9.0
END DESCRIPTION:
XS GIS Cut Line= 3
      1869824.98     13966075.02      1869183.05      13966596.6
      1868824.97     13966925.03
#Sta/Elev= 30
  4162.7  1976.9  4227.1 1962.55  4262.5 1949.74  4360.9 1901.09  4390.4  1884.3
  4416.5 1872.97  4460.8 1860.81  4497.4  1857.4  4654.5 1857.11  4852.2 1859.38
  4866.6 1858.32    4881 1849.73  4887.4 1857.99  4916.2 1856.12  4923.3 1851.85
  4965.7 1847.63  4975.3 1843.63  4975.8 1843.13  4995.3 1843.63  5022.8 1844.15
  5043.7 1851.18  5117.7 1854.86  5228.1 1855.19  5256.5 1859.39  5291.6 1871.95
    5320 1894.32  5352.1 1910.45  5390.9 1928.46  5433.4 1939.17  5475.7 1943.83
#Mann= 8 ,-1 , 0
  4162.7      .1       0  4416.5     .07       0  4654.5    .035       0
  4923.3     .07       0  4975.3     .05       0  4995.3     .07       0
  5117.7    .035       0  5352.1      .1       0
Bank Sta=4975.3,4995.3
XS Rating Curve= 0 ,0
Exp/Cntr=0.3,0.1

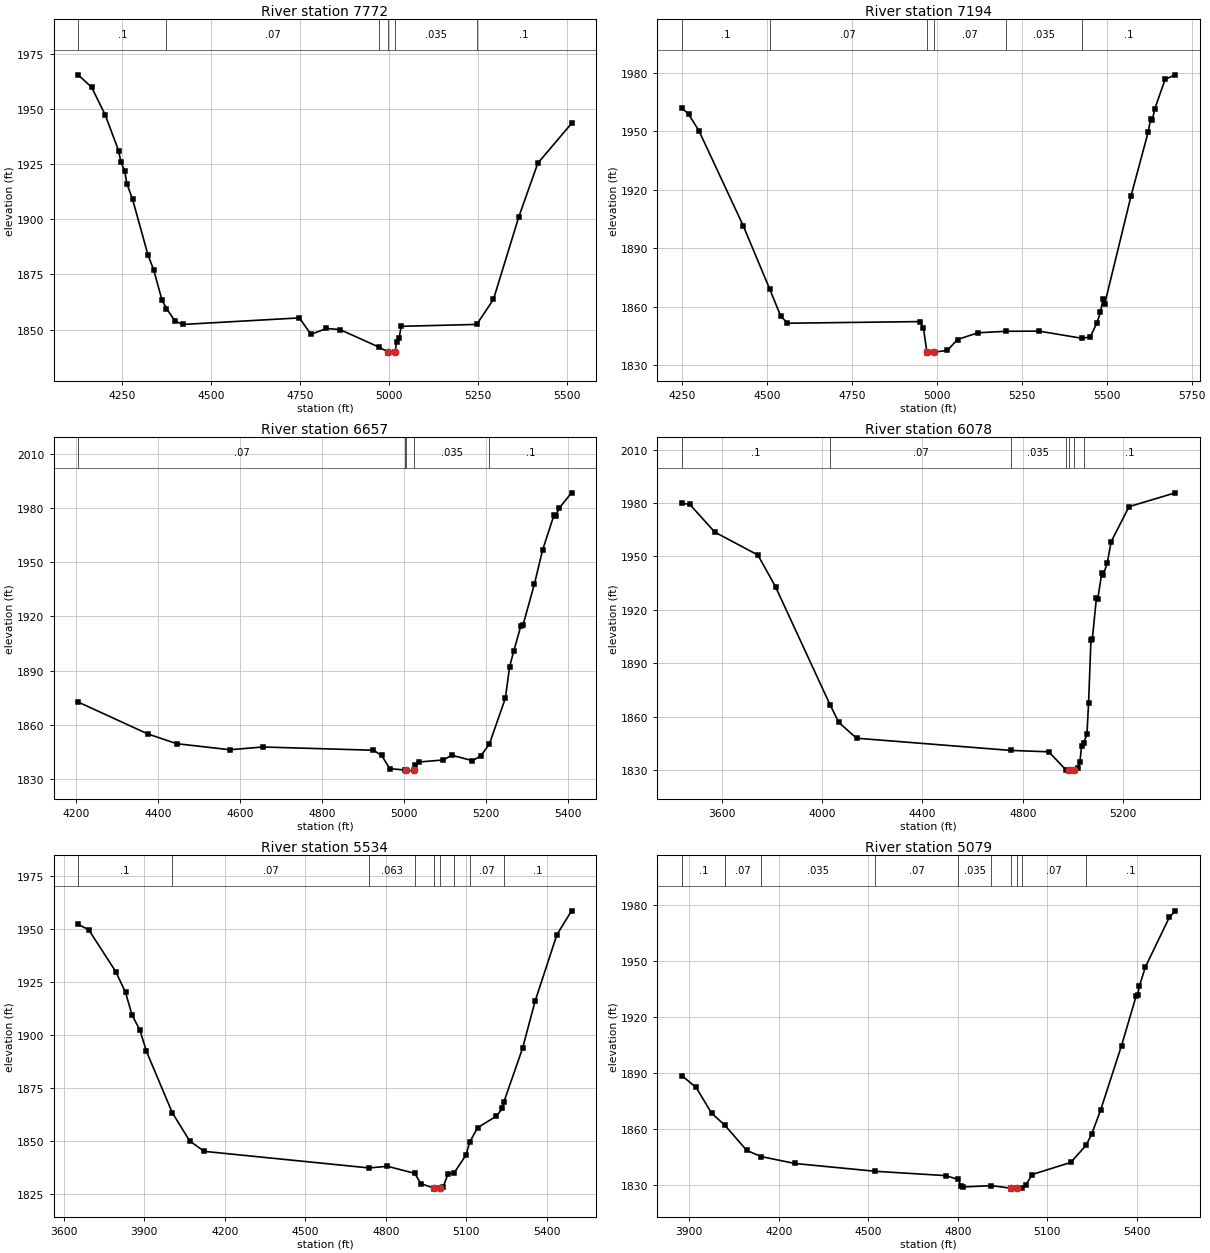
Type RM Length L Ch R = 1 ,7772    ,578,578,578
BEGIN DESCRIPTION:
Dry Branch 8.0
END DESCRIPTION:
XS GIS Cut Line= 3
      1869674.97     13965875.01        1868875.       13966225.
      1868624.98     13966675.03
#Sta/Elev= 30
  4125.9 1965.35  4163.7 1959.71  4202.3 1947.05  4239.3 1931.07  4245.9 1926.07
  4256.9 1921.63  4262.7 1916.11  4278.7 1909.08  4322.3  1883.7  4338.3 1877.03
  4361.7 1863.29  4374.3 1859.53  4398.8 1853.78  4420.6 1852.32    4748 1855.28
  4780.8 1847.85  4824.4  1850.5  4862.3    1850  4970.9 1842.14  4997.1 1839.83
  4997.6 1839.33  5017.1 1839.83    5022 1844.43  5028.8 1846.06  5034.5 1851.47
  5247.2 1852.33  5294.2 1863.68  5365.2  1900.9  5418.9 1925.31  5513.9 1943.36
#Mann= 6 ,-1 , 0
  4125.9      .1       0  4374.3     .07       0  4970.9    .035       0
  4997.1    .035       0  5017.1    .035       0  5247.2      .1       0
Bank Sta=4997.1,5017.1
XS Rating Curve= 0 ,0
Exp/Cntr=0.3,0.1

Type RM Length L Ch R = 1 ,7194    ,537,537,537
BEGIN DESCRIPTION:
Dry Branch 7.0
END DESCRIPTION:
XS GIS Cut Line= 3
      1869624.98       13965675.        1868875.       13965725.
      1868175.03       13965675.
#Sta/Elev= 30
  4248.4 1962.03  4268.4 1958.65  4298.5 1950.27  4428.8 1901.64  4506.4 1869.37
    4539 1855.42  4559.1 1851.62  4949.9 1852.45    4960 1849.09    4970 1836.78
  4970.5 1836.28    4990 1836.78  5030.1 1837.67  5060.2 1843.26  5120.4 1846.71
  5204.4 1847.48  5300.8 1847.55  5426.7 1843.89  5451.2 1844.56  5471.2 1851.87
  5481.3 1857.27  5488.8 1864.13  5493.8 1861.46  5571.5 1916.93  5621.6 1949.44
  5629.1 1956.25  5634.2 1955.91  5641.7 1961.68  5671.8 1976.66  5701.8 1978.98
#Mann= 6 ,-1 , 0
  4248.4      .1       0  4506.4     .07       0    4970     .05       0
    4990     .07       0  5204.4    .035       0  5426.7      .1       0
Bank Sta=4970,4990
XS Rating Curve= 0 ,0
Exp/Cntr=0.3,0.1

Type RM Length L Ch R = 1 ,6657    ,579,579,579
BEGIN DESCRIPTION:
Dry Branch 6.0
END DESCRIPTION:
XS GIS Cut Line= 3
      1869324.96       13965325.        1868525.       13965325.
      1868124.98       13965375.
#Sta/Elev= 30
  4204.8 1872.54  4374.8 1854.86  4444.8 1849.49  4574.8 1846.13  4654.8 1847.66
  4924.8 1845.86  4944.8 1842.95  4964.8 1835.64  5002.5  1834.9  5004.8 1834.79
  5005.3 1834.29  5024.8 1834.79  5024.9 1837.69    5035 1839.33  5095.5 1840.47
  5115.6 1843.11    5166  1840.1  5186.2  1842.6  5207.4 1849.25  5246.6 1874.74
  5256.7 1891.93  5266.8 1900.63  5284.4 1914.83  5289.5 1915.15  5317.2 1937.81
  5337.3 1956.75    5365 1976.02  5370.1 1975.83  5377.6 1979.93  5407.9 1988.41
#Mann= 5 ,-1 , 0
  4204.8     .07       0  5002.5    .035       0  5004.8     .05       0
  5024.8    .035       0  5207.4      .1       0
Bank Sta=5004.8,5024.8
XS Rating Curve= 0 ,0
Exp/Cntr=0.3,0.1

Type RM Length L Ch R = 1 ,6078    ,544,544,544
BEGIN DESCRIPTION:
Dry Branch 5.0
END DESCRIPTION:
XS GIS Cut Line= 3
      1869874.97       13965025.        1868325.       13964825.
      1867975.03     13965024.98
#Sta/Elev= 30
  3441.5  1979.8  3471.7 1979.45  3572.6 1963.68    3744 1950.84  3814.5 1932.94
  4031.9 1866.56  4066.6 1856.71  4137.2 1847.82  4751.4 1840.96  4903.5 1840.17
  4970.7 1830.12  4984.1 1829.81  4984.6 1829.31  5004.3 1829.81    5018  1830.8
  5027.4 1834.62  5033.8  1843.2  5043.1  1845.4  5055.4 1850.03  5061.9  1867.8
  5071.3 1902.97    5077 1903.72  5092.9 1926.45  5098.6 1926.28  5114.5 1940.69
  5120.2 1939.53  5136.1 1946.26  5151.9 1958.36  5223.2 1978.04  5407.4  1985.8
#Mann= 7 ,-1 , 0
  3441.5      .1       0  4031.9     .07       0  4751.4    .035       0
  4970.7     .07       0  4984.1     .05       0  5004.3     .07       0
  5043.1      .1       0
Bank Sta=4984.1,5004.3
XS Rating Curve= 0 ,0
Exp/Cntr=0.3,0.1

Type RM Length L Ch R = 1 ,5534    ,455,455,455
BEGIN DESCRIPTION:
Dry Branch 4.0
END DESCRIPTION:
XS GIS Cut Line= 3
        1869625.       13964825.        1868375.       13964325.
      1867925.03     13964125.02
#Sta/Elev= 30
  3653.7  1952.3  3692.7 1949.79  3793.7 1929.95  3830.1  1920.1  3854.3 1909.47
  3883.9  1902.2  3908.2  1892.2  4004.1 1863.28  4069.7  1849.8  4123.6 1844.95
  4738.1 1837.11  4806.1 1837.89  4907.8 1834.56  4931.3 1829.62  4980.4 1827.59
  4980.9 1827.09  5000.7 1827.59  5014.4 1828.24  5032.1 1834.33  5053.4 1834.57
  5098.5 1843.07  5113.1  1849.4  5142.3 1856.16  5211.3 1861.54  5234.6 1865.23
  5240.4  1868.4  5309.8  1893.7  5356.3 1915.87  5437.7 1947.41  5492.4 1958.72
#Mann= 9 ,-1 , 0
  3653.7      .1       0  4004.1     .07       0  4738.1    .063       0
  4907.8    .035       0  4980.4    .035       0  5000.7    .035       0
  5053.4      .1       0  5113.1     .07       0  5240.4      .1       0
Bank Sta=4980.4,5000.7
XS Rating Curve= 0 ,0
Exp/Cntr=0.3,0.1

Type RM Length L Ch R = 1 ,5079    ,489,489,489
BEGIN DESCRIPTION:
Dry Branch 3.0
END DESCRIPTION:
XS GIS Cut Line= 3
      1869436.19     13964429.42      1868508.93     13963897.97
      1867925.04       13963875.
#Sta/Elev= 30
  3875.8 1888.45  3923.3 1882.18  3975.2 1868.34  4020.3 1861.76  4093.1 1848.33
  4141.4 1845.05  4254.2 1841.35  4524.3 1837.15  4759.2 1834.84  4801.4  1832.8
  4810.8 1829.25  4818.2 1828.75    4913 1829.44  4978.4 1828.08  4978.9 1827.58
  4998.7 1828.08  5015.2  1828.2  5028.6 1829.73  5048.6  1835.4  5178.7 1841.91
    5230 1851.13  5248.7 1857.12  5278.7 1870.01  5348.8 1904.68  5397.8 1931.28
  5402.8 1932.01  5408.8 1936.78  5428.9 1946.89  5508.9 1973.51  5528.9 1977.01
#Mann= 10 ,-1 , 0
  3875.8      .1       0  4020.3     .07       0  4141.4    .035       0
  4524.3     .07       0  4801.4    .035       0    4913    .063       0
  4978.4     .05       0  4998.7    .063       0  5015.2     .07       0
    5230      .1       0
Bank Sta=4978.4,4998.7
XS Rating Curve= 0 ,0
Exp/Cntr=0.3,0.1

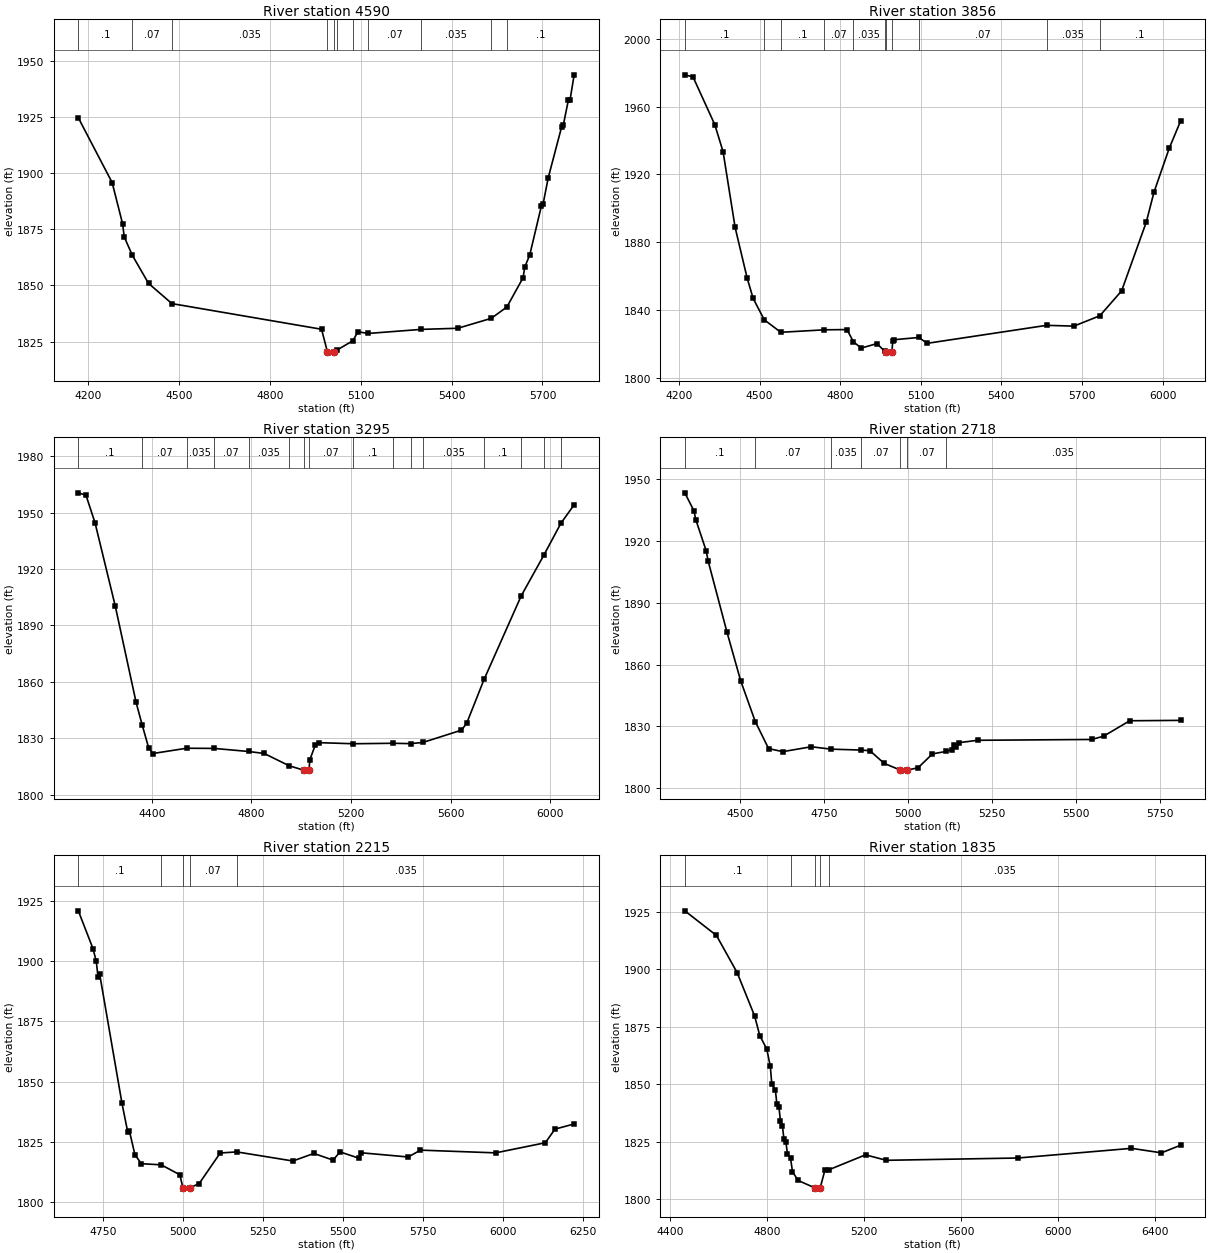
Type RM Length L Ch R = 1 ,4590    ,734,734,734
BEGIN DESCRIPTION:
Mapping XS 926ab5a2
END DESCRIPTION:
XS GIS Cut Line= 4
      1869646.32     13963528.64      1868917.77     13963585.64
      1868367.25     13963574.18      1868049.95     13963737.32
#Sta/Elev= 30
  4166.5 1924.74  4278.2 1895.88  4312.7 1877.52  4318.3  1871.6  4345.1 1863.41
  4398.5 1850.93  4475.7 1841.92  4970.1 1830.49  4989.6 1820.35  4990.1 1819.85
  5010.5 1820.35  5020.9  1821.2  5073.8 1825.39  5090.1 1829.39    5124 1828.62
  5300.1 1830.44  5420.2 1830.93  5530.7 1835.35  5582.3  1840.4  5635.8 1853.42
  5641.6 1858.22    5658 1863.64  5696.7 1885.61  5702.3 1886.48  5718.9 1897.95
  5763.2 1920.64  5768.9 1921.53  5785.4 1932.51    5791 1932.66  5804.7  1943.9
#Mann= 11 ,-1 , 0
  4166.5      .1       0  4345.1     .07       0  4475.7    .035       0
  4989.6    .035       0  5010.5    .035       0  5020.9     .07       0
  5073.8    .035       0    5124     .07       0  5300.1    .035       0
  5530.7     .07       0  5582.3      .1       0
Bank Sta=4989.6,5010.5
XS Rating Curve= 0 ,0
Exp/Cntr=0.3,0.1

Type RM Length L Ch R = 1 ,3856    ,561,561,561
BEGIN DESCRIPTION:
Dry Branch 2.0
END DESCRIPTION:
XS GIS Cut Line= 3
      1869524.99     13962675.01        1868825.       13963025.
      1868025.02     13963724.98
#Sta/Elev= 30
  4221.6 1978.64  4252.3 1977.38  4333.4 1949.26  4364.1 1933.38  4408.9 1888.83
  4453.6 1859.09  4475.9  1847.1  4517.4 1834.47    4579 1827.12  4741.5 1828.58
  4825.3 1828.72  4849.5 1821.46  4878.4 1817.84  4937.1 1820.47  4965.6  1815.9
  4971.4 1815.36  4971.9 1814.86  4992.3 1815.36  4995.8 1822.09  5001.4 1822.77
  5092.3 1824.06  5124.3 1820.64  5568.2 1831.21    5670 1830.76  5766.5 1836.85
  5847.5 1851.48  5939.6 1892.07    5968 1909.57    6025 1935.53  6067.2  1951.5
#Mann= 11 ,-1 , 0
  4221.6      .1       0  4517.4     .07       0    4579      .1       0
  4741.5     .07       0  4849.5    .035       0  4965.6      .1       0
  4971.4     .05       0  4992.3      .1       0  5092.3     .07       0
  5568.2    .035       0  5766.5      .1       0
Bank Sta=4971.4,4992.3
XS Rating Curve= 0 ,0
Exp/Cntr=0.3,0.1

Type RM Length L Ch R = 1 ,3295    ,577,577,577
BEGIN DESCRIPTION:
Dry Branch 1.0
END DESCRIPTION:
XS GIS Cut Line= 3
      1869225.02     13962274.99        1868425.       13962675.
      1867675.02     13963474.98
#Sta/Elev= 30
  4105.3 1960.46  4136.1 1959.17  4172.4  1944.5  4253.5 1900.35  4337.3 1849.07
  4361.3 1837.25  4387.6    1825  4404.4 1821.91  4539.9 1824.71  4650.2 1824.63
  4788.9 1822.99  4851.6 1821.93    4952 1815.39  5010.5 1813.05    5011 1812.55
  5031.4 1813.05  5035.2 1818.71  5056.2 1826.19  5070.3 1827.69  5209.8  1827.1
  5368.1 1827.35  5439.4 1827.16  5488.9 1827.79  5643.8 1834.32  5664.8    1838
  5734.5 1861.28  5883.9 1905.76  5974.9 1927.41  6043.1 1944.29  6096.3 1954.11
#Mann= 16 ,-1 , 0
  4105.3      .1       0  4361.3     .07       0  4539.9    .035       0
  4650.2     .07       0  4788.9    .035       0    4952     .07       0
  5010.5     .05       0  5031.4     .07       0  5209.8      .1       0
  5368.1     .07       0  5439.4      .1       0  5488.9    .035       0
  5734.5      .1       0  5883.9     .07       0  5974.9      .1       0
  6043.1     .07       0
Bank Sta=5010.5,5031.4
XS Rating Curve= 0 ,0
Exp/Cntr=0.3,0.1

Type RM Length L Ch R = 1 ,2718    ,503,503,503
BEGIN DESCRIPTION:
Dry Branch 0.1
END DESCRIPTION:
XS GIS Cut Line= 4
      1869016.85     13962003.78      1868422.19     13962143.84
      1868143.44     13962398.21      1867801.62     13962745.94
#Sta/Elev= 30
  4335.5 1943.42  4362.9 1934.64  4368.2 1930.42    4399 1915.34  4405.2  1910.2
  4460.7    1876  4501.8 1852.19  4545.2 1832.41  4584.9 1819.25  4627.3 1817.78
    4712 1820.15  4771.3 1818.98  4858.6 1818.56  4886.5 1818.23  4928.9 1812.09
  4977.1 1808.82  4977.6 1808.32  4998.1 1808.82  5030.2 1809.99  5072.7 1816.69
  5112.3 1817.85  5129.5 1818.74  5136.3 1821.21  5143.7 1820.02  5150.4 1822.11
  5207.2 1823.29  5546.7 1823.69  5582.1 1825.28  5659.8 1832.77  5811.4 1832.96
#Mann= 7 ,-1 , 0
  4335.5      .1       0  4545.2     .07       0  4771.3    .035       0
  4858.6     .07       0  4977.1     .05       0  4998.1     .07       0
  5112.3    .035       0
Bank Sta=4977.1,4998.1
XS Rating Curve= 0 ,0
Exp/Cntr=0.3,0.1

Type RM Length L Ch R = 1 ,2215    ,380,380,380
BEGIN DESCRIPTION:
Dry Branch 0.0
END DESCRIPTION:
XS GIS Cut Line= 4
      1868900.87     13961786.44      1868424.25     13961736.34
      1868311.25     13961792.13      1867862.36     13962624.43
#Sta/Elev= 30
  4672.5 1920.75  4718.6 1904.99  4728.7 1899.77  4733.9 1893.52    4739 1894.69
  4809.1 1840.91    4827  1829.1    4832 1829.68  4849.3 1819.76  4869.4 1815.95
  4931.8 1815.48  4990.1 1811.36  4999.7 1805.91  5000.2 1805.41  5020.7 1805.91
  5050.4  1807.7  5116.3 1820.39  5168.5 1820.83  5343.6 1817.07  5409.2  1820.2
  5469.2 1817.44  5491.1 1820.84  5551.1 1818.18  5556.8 1820.48  5704.4 1818.73
  5742.5 1821.57  5977.7 1820.44  6133.2 1824.63  6163.4 1830.28  6223.4 1832.42
#Mann= 5 ,-1 , 0
  4672.5      .1       0  4931.8     .07       0  4999.7     .05       0
  5020.7     .07       0  5168.5    .035       0
Bank Sta=4999.7,5020.7
XS Rating Curve= 0 ,0
Exp/Cntr=0.3,0.1

Type RM Length L Ch R = 1 ,1835    ,893,893,893
BEGIN DESCRIPTION:
Dry Branch 0.3
END DESCRIPTION:
XS GIS Cut Line= 5
      1868997.31     13961806.27      1868704.37     13961424.36
      1868574.16     13961359.25      1868198.72     13961632.69
      1867862.36     13962524.61
#Sta/Elev= 30
  4459.8 1925.47  4590.3 1914.75  4675.7 1898.55  4748.1 1879.59  4768.9 1871.14
  4797.9 1865.25  4812.4 1857.74  4818.7 1849.92  4833.2 1847.57  4839.5 1841.32
  4847.8 1840.26  4854.1 1834.06  4862.3 1831.77  4868.6 1826.15  4876.8 1824.75
  4883.1 1819.75  4895.8 1817.76  4903.9 1811.93  4926.6  1808.1    4997  1804.8
  4997.5  1804.3    5018  1804.8  5037.9 1812.71  5056.4 1812.84    5205 1819.23
  5290.8 1816.85  5833.9 1817.85  6301.8 1822.06  6425.4  1820.1  6504.4 1823.42
#Mann= 5 ,-1 , 0
  4459.8      .1       0  4895.8     .07       0    4997     .05       0
    5018     .07       0  5056.4    .035       0
Bank Sta=4997,5018
XS Rating Curve= 0 ,0
Exp/Cntr=0.3,0.1

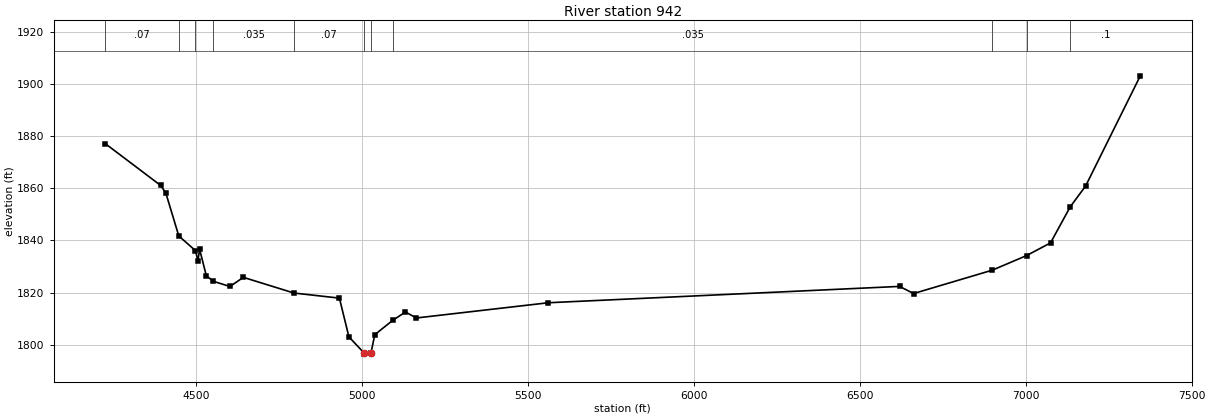
Type RM Length L Ch R = 1 ,942     ,0,0,0
BEGIN DESCRIPTION:
Dry Branch 0.2
END DESCRIPTION:
XS GIS Cut Line= 4
      1869154.63     13960710.41      1868519.18       13960825.
      1868331.68     13961048.96      1867618.41     13963110.68
#Sta/Elev= 30
  4225.8 1877.06  4392.8 1861.03  4408.3 1858.13  4447.3  1841.7  4497.6 1836.07
    4505 1832.26  4510.1 1836.56  4530.3 1826.48  4550.8 1824.36  4601.4 1822.35
    4642 1825.84  4794.5 1819.84  4931.4 1817.89    4960 1803.06  5005.3 1796.94
  5005.8 1796.44  5026.6 1796.94    5038 1803.89  5092.4 1809.41  5130.4 1812.56
  5163.6 1810.29  5561.3 1816.12  6619.6 1822.38    6662 1819.65  6899.4 1828.61
  7002.3 1834.18  7074.6 1839.04    7134 1852.85  7180.5 1860.86  7345.2 1903.03
#Mann= 11 ,-1 , 0
  4225.8     .07       0  4447.3    .035       0  4497.6      .1       0
  4550.8    .035       0  4794.5     .07       0  5005.3     .05       0
  5026.6     .07       0  5092.4    .035       0  6899.4    .063       0
  7002.3    .035       0    7134      .1       0
Bank Sta=5005.3,5026.6
XS Rating Curve= 0 ,0
Exp/Cntr=0.3,0.1

Chan Stop Cuts=-1
Use User Specified Reach Order=0
Composite Channel Slope=5