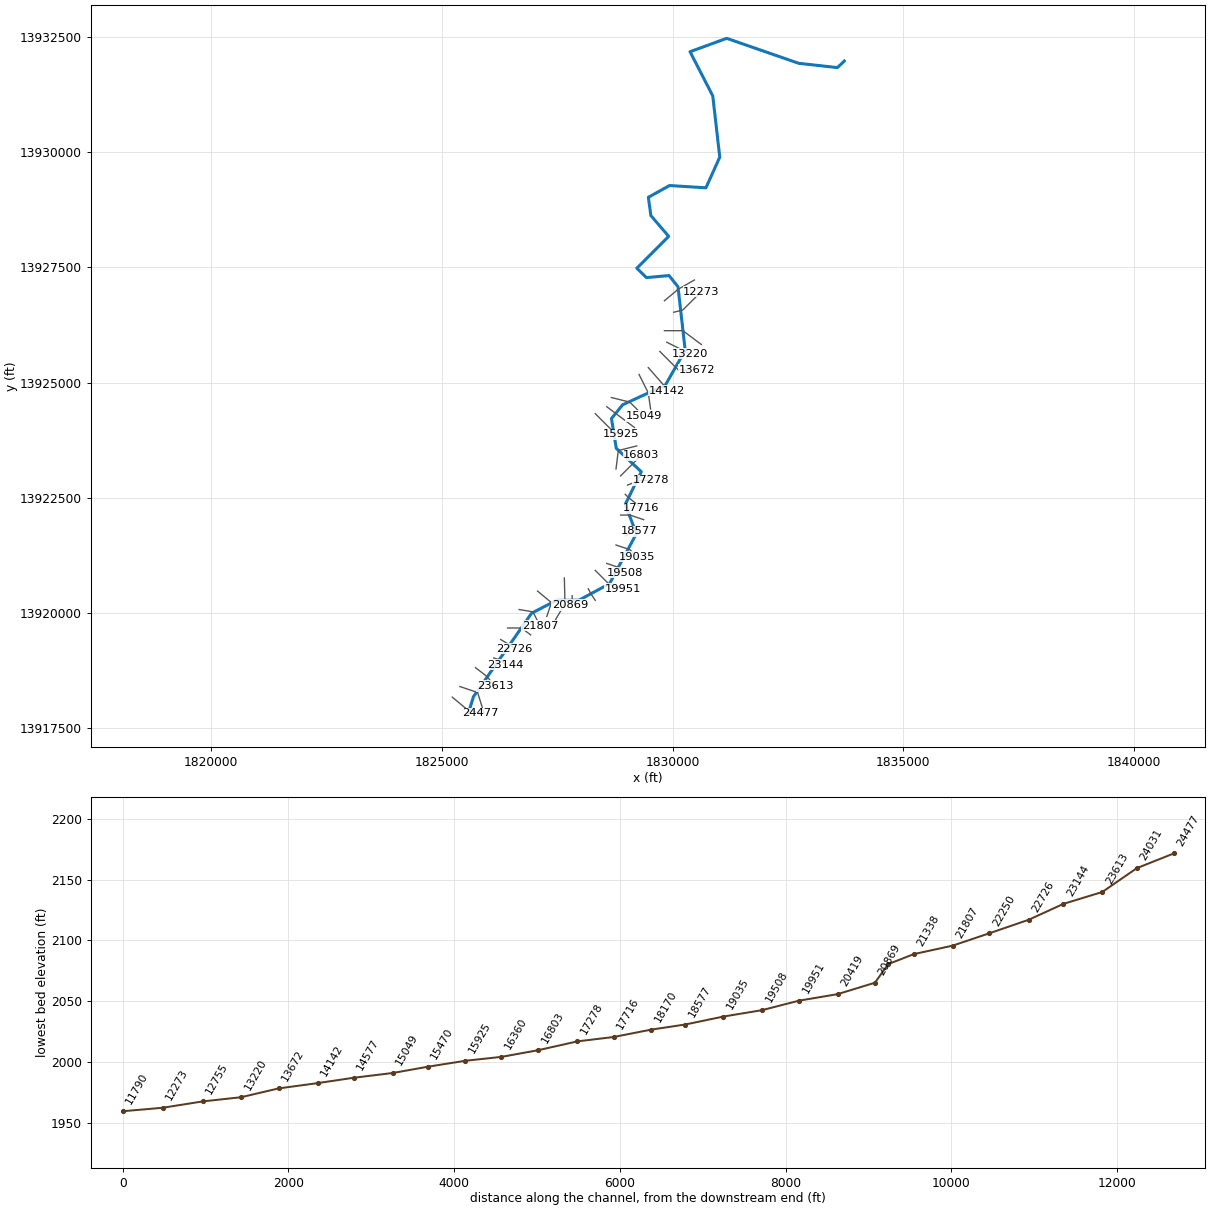
--- Dry Creek.prj (project) ---

Proj Title=Dry Creek Base Level Engineering
Current Plan=p01
Default Exp/Contr=0.3,0.1
English Units
Geom File=g01
Flow File=f01
Plan File=p01
Y Axis Title=Elevation
X Axis Title(PF)=Main Channel Distance
X Axis Title(XS)=Station
BEGIN DESCRIPTION:
Dry Creek
END DESCRIPTION:
DSS Export Rating Curves= 0
DSS Export Rating Curve Sorted= 0
DSS Export Volume Flow Curves= 0
DXF OffsetX= 0
DXF OffsetY= 0
DXF ScaleX= 1
DXF ScaleY= 10

--- Dry Creek.p01 (plan) ---

Plan Title=Multiple Run
Short Identifier=Multiple
Geom File=g01
Flow File=f01
Subcritical Flow
K Sum by GR= 0
Std Step Tol= 0.01
Critical Tol= 0.01
Num of Std Step Trials= 20
Max Error Tol= 0.3
Flow Tol Ratio= 0.001
Split Flow NTrial= 30
Split Flow Tol= 0.02
Split Flow Ratio= 0.02
Log Output Level= 0
Friction Slope Method= 1
Unsteady Friction Slope Method= 2
Unsteady Bridges Friction Slope Method= 1
Parabolic Critical Depth
Global Vel Dist=  1 , 1 , 1
Global Log Level= 0
CheckData=True
Encroach Param= -1, 0, 0, 0
BEGIN DESCRIPTION:
Multiple Run
END DESCRIPTION:

--- Dry Creek.f01 (steady flow) ---

Flow Title=Multiple
Number of Profiles=7
Profile Names=10-year,25-year,50-year,1pct_min,100-year,1pct_plu,500-year
River Rch & RM= Dry Creek,Reach-1,24477
     280     438     577     370     738    1472    1185
River Rch & RM= Dry Creek,Reach-1,22726
    1622    2853    4057    2786    5558   11090   10316
River Rch & RM= Dry Creek,Reach-1,15925
    2207    3929    5631    3891    7763   15489   14599
River Rch & RM= Dry Creek,Reach-1,9995
    2445    4369    6278    4347    8674   17307   16386
River Rch & RM= Dry Creek,Reach-1,7142
    2739    4909    7069    4901    9779   19511   18523
Boundary for River Rch & Prof#=Dry Creek,Reach-1,1
Up Type=0
Dn Type=3
Dn Slope=0.005
Boundary for River Rch & Prof#=Dry Creek,Reach-1,2
Up Type=0
Dn Type=3
Dn Slope=0.005
Boundary for River Rch & Prof#=Dry Creek,Reach-1,3
Up Type=0
Dn Type=3
Dn Slope=0.005
Boundary for River Rch & Prof#=Dry Creek,Reach-1,4
Up Type=0
Dn Type=3
Dn Slope=0.005
Boundary for River Rch & Prof#=Dry Creek,Reach-1,5
Up Type=0
Dn Type=3
Dn Slope=0.005
Boundary for River Rch & Prof#=Dry Creek,Reach-1,6
Up Type=0
Dn Type=3
Dn Slope=0.005
Boundary for River Rch & Prof#=Dry Creek,Reach-1,7
Up Type=0
Dn Type=3
Dn Slope=0.005

--- Dry Creek.g01 (geometry) ---

Geom Title=Existing Conditions
Program Version=4.10

River Reach=Dry Creek       ,Reach-1
Reach XY= 30
        1825575.       13917825.      1825682.88     13918181.16
      1826944.77     13919995.13      1827480.52     13920272.65
      1827973.45     13920278.75      1828634.81     13920635.51
      1829216.98     13921721.69      1828974.75     13922356.54
      1829323.92     13923064.46      1828780.83      13923572.7
      1828676.62     13924218.97      1828918.66     13924516.98
      1829845.09     13924944.79       1830275.2     13925699.92
      1830119.17      13927077.3      1829923.75     13927321.55
      1829434.59      13927276.2      1829226.69     13927480.64
      1829916.98     13928171.69      1829530.52     13928622.57
      1829477.06     13929019.15       1829935.5     13929273.78
        1830725.       13929225.      1831024.48     13929890.22
      1830872.81     13931219.56      1830380.09      13932177.3
       1831175.1     13932467.68       1832735.5      13931926.2
       1833575.1     13931832.31        1833725.       13931975.

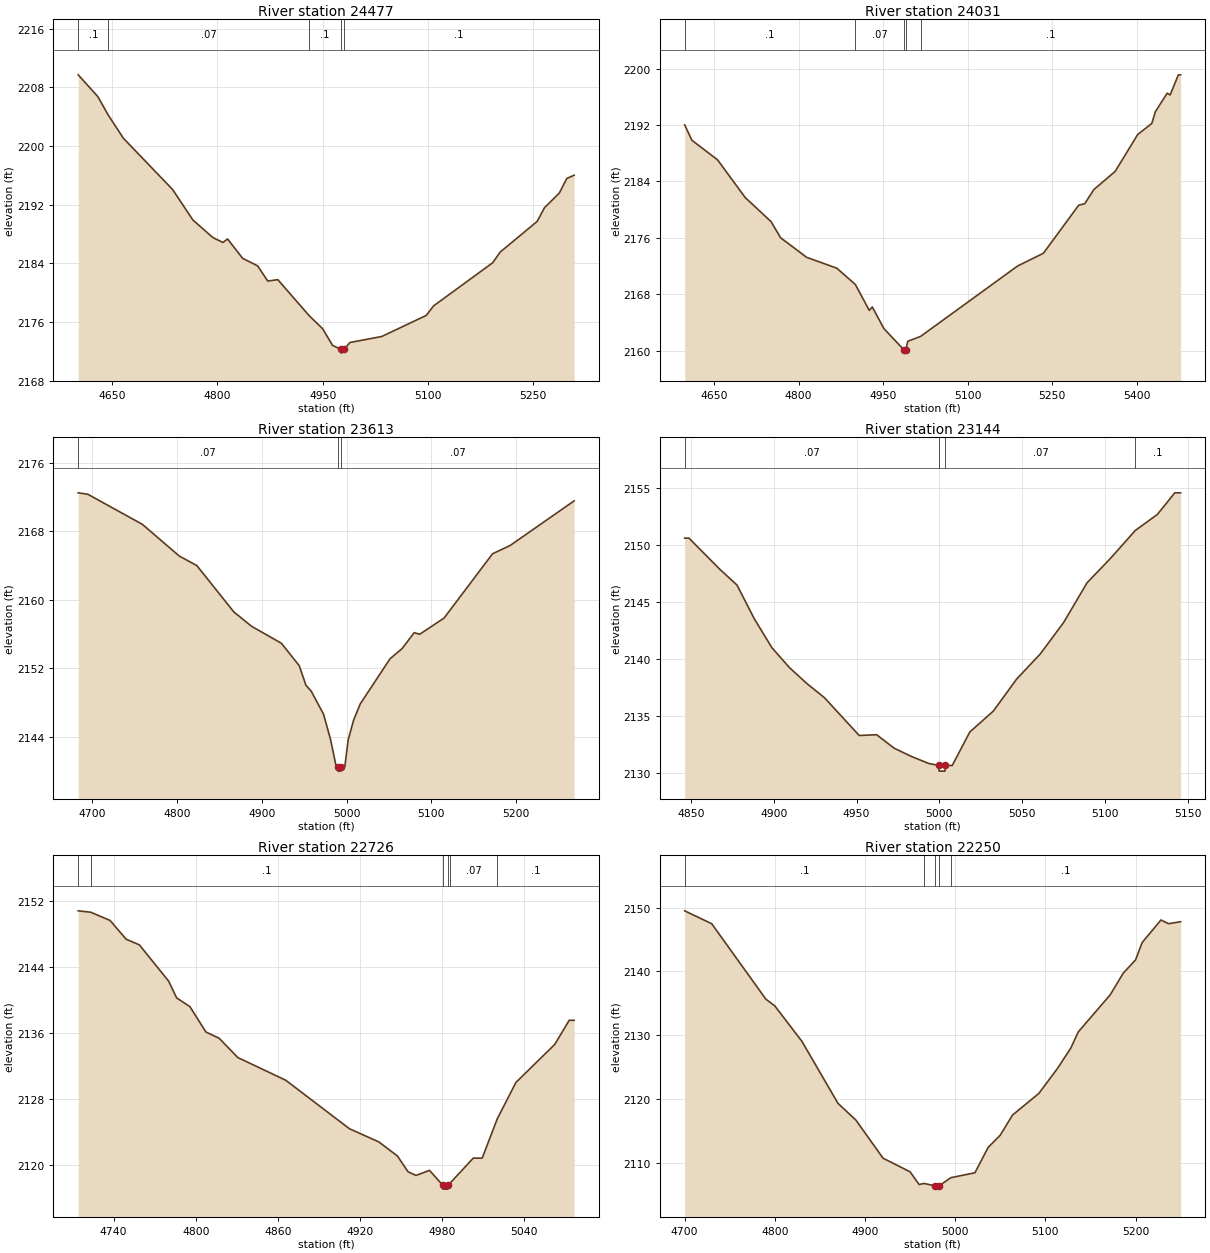
Type RM Length L Ch R = 1 ,24477   ,446,446,446
BEGIN DESCRIPTION:
Dry Creek 52.0
END DESCRIPTION:
XS GIS Cut Line= 3
      1825225.03     13918174.97        1825525.       13917925.
        1825825.       13917825.
#Sta/Elev= 30
  4601.7  2209.7  4629.6 2206.74  4644.6  2204.2  4666.1 2201.05  4736.4 2194.04
    4765 2189.92  4793.7  2187.5    4808 2186.84  4814.5 2187.32    4836 2184.68
  4857.4 2183.65  4871.8 2181.58  4886.1 2181.77  4930.9 2176.85  4949.9 2175.09
  4964.2  2172.8  4976.5 2172.25  4976.8 2171.75  4980.5 2172.25  4988.9  2173.2
  5034.3 2174.02  5097.6 2176.89  5108.1 2178.19  5192.4 2184.08    5203 2185.53
  5255.7 2189.71  5266.2 2191.59  5287.3 2193.58  5297.9 2195.57  5308.4 2196.01
#Mann= 5 ,-1 , 0
  4601.7      .1       0  4644.6     .07       0  4930.9      .1       0
  4976.5     .05       0  4980.5      .1       0
Bank Sta=4976.5,4980.5
XS Rating Curve= 0 ,0
Exp/Cntr=0.3,0.1

Type RM Length L Ch R = 1 ,24031   ,418,418,418
BEGIN DESCRIPTION:
Dry Creek 51.0
END DESCRIPTION:
XS GIS Cut Line= 3
      1825389.74     13918404.81        1825775.       13918275.
      1825915.55     13917822.36
#Sta/Elev= 30
  4597.8 2192.02  4610.7 2189.83  4656.1 2187.07  4705.2 2181.72  4751.1  2178.3
  4768.2    2176  4814.4 2173.23  4867.9 2171.69  4900.9 2169.37  4925.6  2165.7
  4930.9 2166.19  4951.6 2163.11  4986.6 2160.14  4986.8 2159.64  4990.6 2160.14
  4993.9 2161.32  5016.8 2162.02  5188.7 2171.99  5234.7 2173.81  5297.5 2180.64
    5308 2180.83  5324.2 2182.84    5362 2185.41  5402.2 2190.66  5427.1 2192.22
  5433.7 2193.92  5454.5 2196.52  5459.7 2196.26  5474.3 2199.12  5478.3 2199.12
#Mann= 5 ,-1 , 0
  4597.8      .1       0  4900.9     .07       0  4986.6     .05       0
  4990.6     .07       0  5016.8      .1       0
Bank Sta=4986.6,4990.6
XS Rating Curve= 0 ,0
Exp/Cntr=0.3,0.1

Type RM Length L Ch R = 1 ,23613   ,469,469,469
BEGIN DESCRIPTION:
Dry Creek 50.0
END DESCRIPTION:
XS GIS Cut Line= 3
      1825728.33     13918814.89        1825975.       13918625.
      1826150.87     13918415.02
#Sta/Elev= 30
  4683.4 2172.47  4694.8  2172.3  4759.1 2168.79  4802.6 2165.09  4823.4 2163.97
    4867 2158.56  4887.8 2156.89  4923.1  2154.9  4944.2 2152.28  4952.1    2150
  4958.4 2149.29  4972.9 2146.61  4981.1 2143.68  4987.4  2140.7  4989.5 2140.46
  4989.8 2139.96  4993.3 2139.96  4993.5 2140.46    4998 2140.46  5001.9 2143.59
  5008.4 2145.93  5016.2 2147.81  5051.3 2153.08  5065.6 2154.28  5079.9 2156.14
  5086.4 2155.95  5115.1 2157.84  5172.3 2165.35  5193.1 2166.32  5268.6 2171.53
#Mann= 3 ,-1 , 0
  4683.4     .07       0  4989.5     .05       0  4993.5     .07       0
Bank Sta=4989.5,4993.5
XS Rating Curve= 0 ,0
Exp/Cntr=0.3,0.1

Type RM Length L Ch R = 1 ,23144   ,418,418,418
BEGIN DESCRIPTION:
Dry Creek 49.0
END DESCRIPTION:
XS GIS Cut Line= 3
      1826125.01       13919025.        1826275.       13918975.
      1826374.99     13918875.01
#Sta/Elev= 30
  4846.2 2150.58  4848.8 2150.58  4867.3 2147.87  4877.8 2146.47  4888.3  2143.5
  4898.9 2140.98  4909.4 2139.25    4920 2137.84  4930.5 2136.62  4951.6 2133.29
  4962.1 2133.36  4972.7 2132.18  4983.2 2131.45  4993.8 2130.83  4999.7 2130.67
  4999.9 2130.17  5003.4 2130.17  5003.7 2130.67  5007.8 2130.67  5018.4  2133.6
  5032.6 2135.43  5046.7 2138.24  5060.9 2140.43    5075 2143.18  5089.2 2146.67
  5103.3  2148.8  5118.3 2151.25  5131.6 2152.65  5142.2 2154.55  5145.7 2154.55
#Mann= 4 ,-1 , 0
  4846.2     .07       0  4999.7     .05       0  5003.7     .07       0
  5118.3      .1       0
Bank Sta=4999.7,5003.7
XS Rating Curve= 0 ,0
Exp/Cntr=0.3,0.1

Type RM Length L Ch R = 1 ,22726   ,476,476,476
BEGIN DESCRIPTION:
Dry Creek 48.0
END DESCRIPTION:
XS GIS Cut Line= 3
        1826275.       13919425.        1826525.       13919275.
      1826575.03     13919224.97
#Sta/Elev= 30
  4714.1 2150.86  4723.3 2150.69  4737.4 2149.69  4749.1 2147.42  4758.8 2146.73
  4780.2 2142.32    4786  2140.3  4795.7 2139.24  4807.4 2136.16  4817.1  2135.4
  4830.7 2133.06  4865.7 2130.31  4912.3 2124.42  4933.7 2122.83  4947.3 2121.12
  4955.1  2119.2  4960.9 2118.76  4970.7 2119.38  4980.3  2117.6  4980.6  2117.1
  4984.1  2117.1  4984.3  2117.6  4985.4 2117.76  5002.7 2120.86  5009.2 2120.86
  5020.3 2125.65  5033.9 2130.05  5062.2 2134.65  5072.8 2137.58  5076.4 2137.58
#Mann= 6 ,-1 , 0
  4714.1     .07       0  4723.3      .1       0  4980.3     .05       0
  4984.3      .1       0  4985.4     .07       0  5020.3      .1       0
Bank Sta=4980.3,4984.3
XS Rating Curve= 0 ,0
Exp/Cntr=0.3,0.1

Type RM Length L Ch R = 1 ,22250   ,443,443,443
BEGIN DESCRIPTION:
Dry Creek 47.0
END DESCRIPTION:
XS GIS Cut Line= 3
      1826424.96       13919675.        1826725.       13919675.
      1826924.97     13919525.03
#Sta/Elev= 30
    4700 2149.49    4730 2147.47    4790 2135.67    4800  2134.6    4830 2129.07
    4870 2119.36    4890 2116.72    4920 2110.77    4950 2108.64    4960 2106.65
  4965.4 2106.82    4978 2106.43  4978.3 2105.93    4982 2106.43  4995.2 2107.72
  5021.9 2108.49  5036.5 2112.45    5050 2114.38  5063.6 2117.53  5092.8 2120.91
  5113.6 2124.85  5128.2    2128  5136.5 2130.54  5171.9 2136.34  5186.5 2139.76
    5200  2141.8  5207.3 2144.52  5228.2 2148.06  5236.5 2147.48    5250 2147.78
#Mann= 5 ,-1 , 0
    4700      .1       0  4965.4     .07       0    4978     .05       0
    4982     .07       0  4995.2      .1       0
Bank Sta=4978,4982
XS Rating Curve= 0 ,0
Exp/Cntr=0.3,0.1

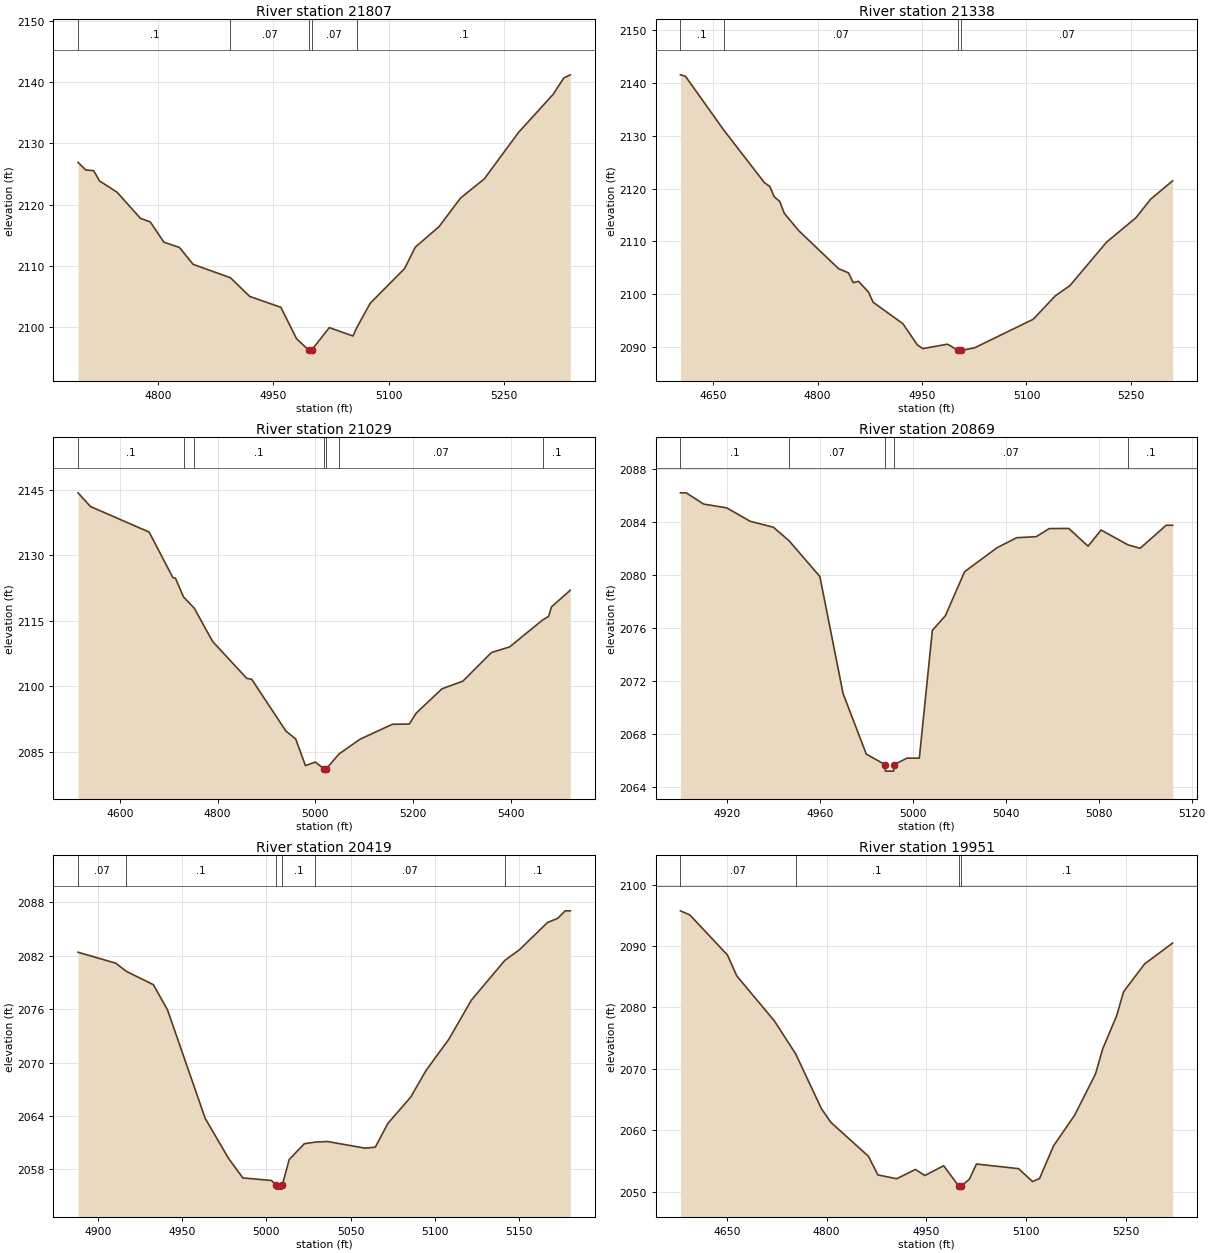
Type RM Length L Ch R = 1 ,21807   ,469,469,469
BEGIN DESCRIPTION:
Dry Creek 46.0
END DESCRIPTION:
XS GIS Cut Line= 3
      1826674.98       13920075.        1826975.       13920025.
      1827125.01     13919724.97
#Sta/Elev= 30
  4696.4 2126.91  4706.6 2125.66  4716.7 2125.56  4724.3 2123.88  4747.1 2122.04
  4777.5 2117.77  4790.2  2117.2  4807.9 2113.88  4828.2 2113.01    4846 2110.25
  4894.5 2108.06  4919.5 2105.01    4960 2103.23  4980.3 2098.12    4996 2096.25
  4996.3 2095.75    5000 2096.25  5022.9 2099.92  5053.7 2098.55  5058.6 2099.92
    5076 2103.89  5120.7 2109.56  5134.7 2113.07  5165.5 2116.41  5193.4 2121.08
  5224.2  2124.2  5268.9 2131.82  5313.6    2138  5327.6  2140.7    5336 2141.21
#Mann= 5 ,-1 , 0
  4696.4      .1       0  4894.5     .07       0    4996     .05       0
    5000     .07       0  5058.6      .1       0
Bank Sta=4996,5000
XS Rating Curve= 0 ,0
Exp/Cntr=0.3,0.1

Type RM Length L Ch R = 1 ,21338   ,309,309,309
BEGIN DESCRIPTION:
Dry Creek 45.0
END DESCRIPTION:
XS GIS Cut Line= 3
      1827074.97     13920475.02        1827375.       13920225.
      1827274.99     13919924.97
#Sta/Elev= 30
  4603.1 2141.58  4610.3 2141.31  4665.6 2131.05  4723.5 2121.15  4731.4 2120.39
  4737.9 2118.41  4745.7 2117.56  4752.2 2115.31    4773    2112  4830.3 2104.78
  4844.6 2103.98  4851.1 2102.13  4858.9 2102.39  4873.2 2100.33  4879.7 2098.43
  4922.7 2094.33  4943.5 2090.29  4951.3 2089.62  4986.5 2090.46  5002.2 2089.26
  5002.4 2088.76  5006.2 2089.26  5025.3 2089.76  5109.6 2095.18  5141.2 2099.61
  5162.3 2101.57    5215 2109.82  5257.2 2114.46  5278.3 2117.98  5309.9 2121.47
#Mann= 4 ,-1 , 0
  4603.1      .1       0  4665.6     .07       0  5002.2     .05       0
  5006.2     .07       0
Bank Sta=5002.2,5006.2
XS Rating Curve= 0 ,0
Exp/Cntr=0.3,0.1

Type RM Length L Ch R = 1 ,21029   ,160,160,160
BEGIN DESCRIPTION:
Dry Creek 44.1
END DESCRIPTION:
XS GIS Cut Line= 4
      1827655.17     13920760.52      1827666.74     13920285.94
      1827645.27     13920162.29      1827437.72      13919811.4
#Sta/Elev= 30
  4514.2 2144.27  4539.7 2141.13  4659.8 2135.28  4708.6 2124.81  4713.6 2124.74
  4730.2 2120.42  4752.1 2117.86  4789.8 2110.21  4859.8 2101.75  4869.8 2101.56
  4939.8  2089.7  4959.9 2087.88  4979.9 2081.77    5000 2082.59  5018.3 2081.01
  5018.6 2080.51  5022.3 2081.01  5048.7 2084.45  5091.6 2087.82  5157.7 2091.24
  5192.6  2091.3  5206.7 2093.81  5259.4 2099.37  5302.3 2101.13  5360.8 2107.69
  5397.8 2108.96  5465.3 2115.12  5477.8 2115.96  5483.6 2118.14  5522.1 2121.95
#Mann= 7 ,-1 , 0
  4514.2      .1       0  4730.2     .07       0  4752.1      .1       0
  5018.3     .05       0  5022.3      .1       0  5048.7     .07       0
  5465.3      .1       0
Bank Sta=5018.3,5022.3
XS Rating Curve= 0 ,0
Exp/Cntr=0.3,0.1

Type RM Length L Ch R = 1 ,20869   ,450,450,450
BEGIN DESCRIPTION:
Dry Creek 44.0
END DESCRIPTION:
XS GIS Cut Line= 3
        1827825.     13920374.98        1827825.       13920275.
      1827774.99     13920174.98
#Sta/Elev= 30
    4900 2086.22  4902.5 2086.22    4910 2085.37    4920 2085.08    4930 2084.07
    4940 2083.62  4946.7 2082.61    4960  2079.9    4970 2071.05    4980 2066.48
    4988  2065.7  4988.2  2065.2  4991.7  2065.2    4992  2065.7  4997.5 2066.18
  5002.8 2066.18  5008.4 2075.83    5014 2076.94  5022.3 2080.27  5036.3 2082.08
  5044.7 2082.83  5053.1 2082.91  5058.7 2083.52  5067.1 2083.53  5075.4 2082.19
    5081 2083.41  5092.6 2082.29  5097.8 2082.03    5109 2083.77  5111.8 2083.77
#Mann= 5 ,-1 , 0
    4900      .1       0  4946.7     .07       0    4988     .05       0
    4992     .07       0  5092.6      .1       0
Bank Sta=4988,4992
XS Rating Curve= 0 ,0
Exp/Cntr=0.3,0.1

Type RM Length L Ch R = 1 ,20419   ,468,468,468
BEGIN DESCRIPTION:
Dry Creek 43.0
END DESCRIPTION:
XS GIS Cut Line= 3
        1828175.       13920525.        1828225.       13920425.
      1828325.01     13920274.99
#Sta/Elev= 30
  4888.2 2082.39  4910.6 2081.16  4916.9 2080.24  4932.9 2078.75  4941.3 2075.92
  4963.7 2063.72  4977.6 2059.22    4986 2057.05    5003 2056.76  5005.5 2056.29
  5005.8 2055.79  5009.3 2055.79  5009.5 2056.29  5013.5 2059.11  5022.5 2060.89
    5029 2061.07  5036.1 2061.14  5058.6 2060.39  5064.6  2060.5  5072.1 2063.18
  5085.6 2066.12  5094.7 2069.11  5108.2 2072.61  5121.7 2077.03  5141.5 2081.48
  5150.2 2082.68  5166.8 2085.73  5172.8 2086.19  5177.3 2087.04  5180.3 2087.04
#Mann= 6 ,-1 , 0
  4888.2     .07       0  4916.9      .1       0  5005.5     .05       0
  5009.5      .1       0    5029     .07       0  5141.5      .1       0
Bank Sta=5005.5,5009.5
XS Rating Curve= 0 ,0
Exp/Cntr=0.3,0.1

Type RM Length L Ch R = 1 ,19951   ,443,443,443
BEGIN DESCRIPTION:
Dry Creek 42.0
END DESCRIPTION:
XS GIS Cut Line= 3
      1828325.01     13920924.99        1828625.       13920625.
      1828925.02     13920524.99
#Sta/Elev= 30
  4580.1 2095.73  4594.2 2095.07  4650.8 2088.54  4664.9 2085.12  4721.5 2077.79
  4753.4 2072.44  4792.2  2063.5  4806.4 2061.27  4862.9 2055.75  4877.1 2052.71
  4905.4 2052.08  4933.6  2053.6  4947.8 2052.61  4976.1  2054.2  4998.8 2050.89
  4999.1 2050.39  5002.8 2050.89  5014.9 2052.02  5025.4 2054.48  5088.7 2053.73
  5109.8 2051.63  5120.3 2052.12  5141.4 2057.43    5173 2062.41  5204.6 2069.17
  5215.2 2073.19  5236.3 2078.63  5246.8 2082.55  5278.4 2087.08  5320.6 2090.49
#Mann= 4 ,-1 , 0
  4580.1     .07       0  4753.4      .1       0  4998.8     .05       0
  5002.8      .1       0
Bank Sta=4998.8,5002.8
XS Rating Curve= 0 ,0
Exp/Cntr=0.3,0.1

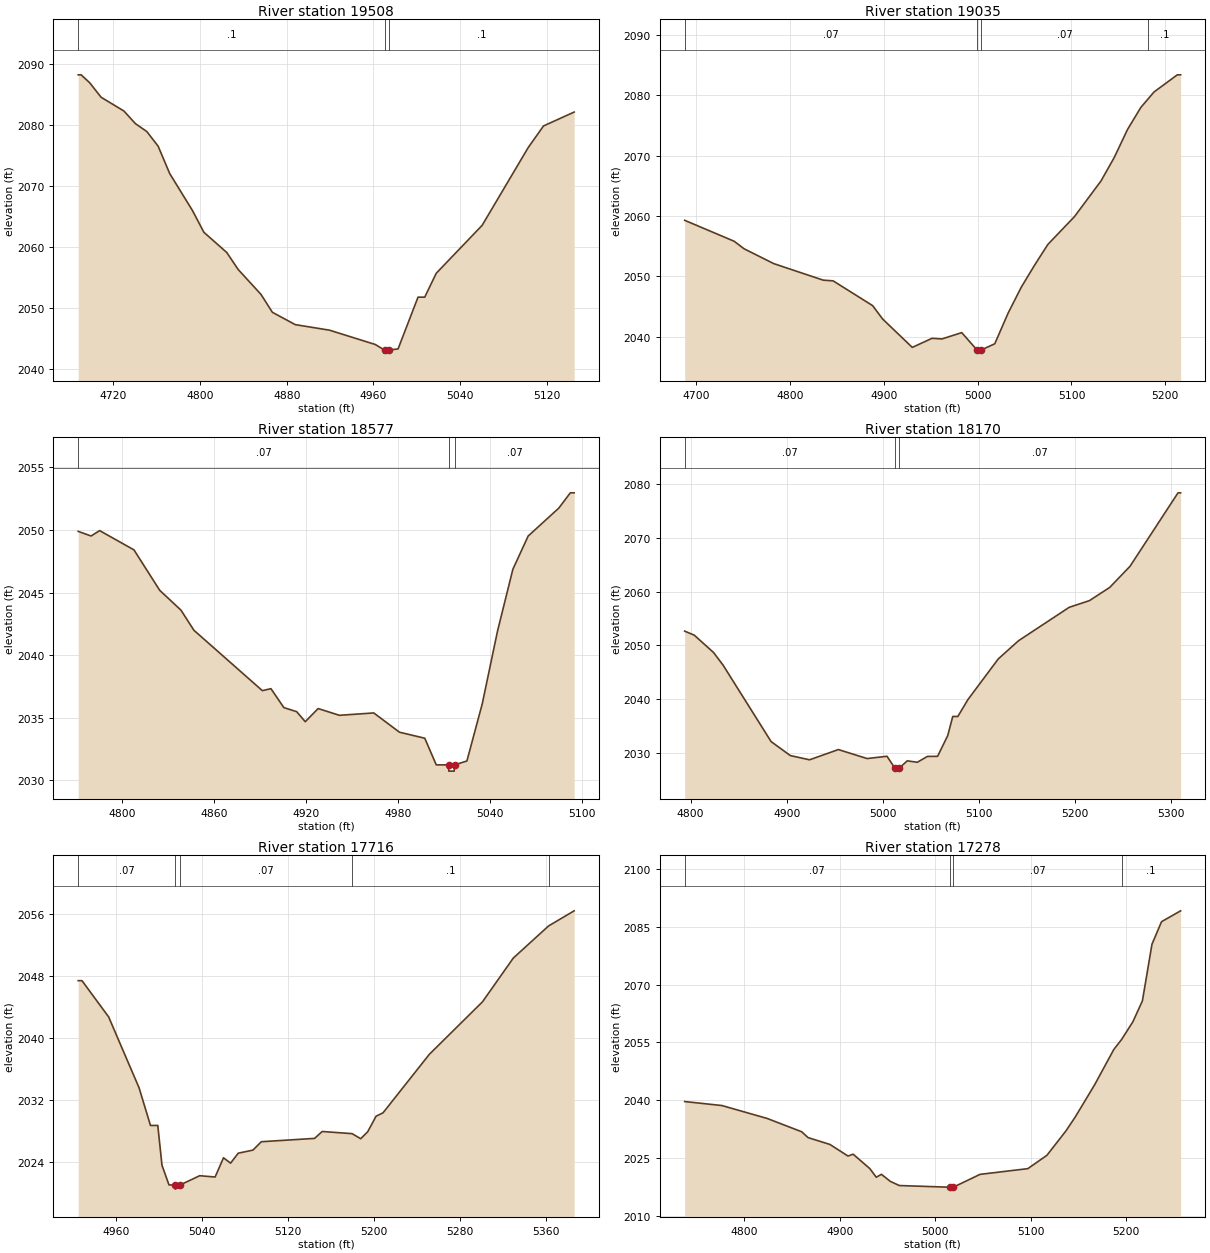
Type RM Length L Ch R = 1 ,19508   ,473,473,473
BEGIN DESCRIPTION:
Dry Creek 41.0
END DESCRIPTION:
XS GIS Cut Line= 3
      1828574.96     13921075.01        1828875.       13920975.
        1828975.       13920875.
#Sta/Elev= 30
  4687.6 2088.21  4690.3 2088.21  4698.2 2086.91  4708.7 2084.54  4729.8 2082.28
  4740.4 2080.21  4750.9 2078.92  4761.4 2076.51    4772 2072.05  4793.1 2065.96
  4803.6 2062.41  4824.7  2059.1  4835.2 2056.32  4856.3 2052.23  4866.8  2049.3
  4887.9 2047.28  4919.5 2046.37  4961.7 2044.03  4970.3 2043.11  4970.5 2042.61
    4974 2042.61  4974.3 2043.11  4982.8  2043.3  5001.2 2051.78  5007.4 2051.78
    5018 2055.69  5060.4 2063.55  5102.9 2076.29    5117 2079.83  5145.3 2082.11
#Mann= 3 ,-1 , 0
  4687.6      .1       0  4970.3     .05       0  4974.3      .1       0
Bank Sta=4970.3,4974.3
XS Rating Curve= 0 ,0
Exp/Cntr=0.3,0.1

Type RM Length L Ch R = 1 ,19035   ,458,458,458
BEGIN DESCRIPTION:
Dry Creek 40.0
END DESCRIPTION:
XS GIS Cut Line= 3
      1828774.96     13921475.01        1829075.       13921375.
        1829225.       13921225.
#Sta/Elev= 30
  4687.9 2059.27  4740.6  2055.8  4751.2 2054.55  4782.8 2052.09  4835.5 2049.35
  4846.1 2049.23  4888.2 2045.12  4898.8 2042.91  4930.4  2038.2  4951.5 2039.71
    4962  2039.6  4983.1 2040.65  4999.5 2037.75  4999.8 2037.25  5003.3 2037.25
  5003.5 2037.75  5018.3  2038.8  5032.5 2043.88  5046.6  2048.2  5060.7 2051.83
  5074.9 2055.28  5103.2 2059.88  5131.5  2065.8  5145.6 2069.69  5159.7 2074.32
  5173.9 2077.98  5181.9 2079.44    5188 2080.55  5212.8 2083.39  5216.3 2083.39
#Mann= 4 ,-1 , 0
  4687.9     .07       0  4999.5     .05       0  5003.5     .07       0
  5181.9      .1       0
Bank Sta=4999.5,5003.5
XS Rating Curve= 0 ,0
Exp/Cntr=0.3,0.1

Type RM Length L Ch R = 1 ,18577   ,407,407,407
BEGIN DESCRIPTION:
Dry Creek 39.0
END DESCRIPTION:
XS GIS Cut Line= 3
      1828974.96     13921674.98        1829175.       13921775.
      1829275.05       13921775.
#Sta/Elev= 30
  4771.1 2049.89  4779.5 2049.52  4785.1 2049.95  4807.5 2048.41  4824.3 2045.18
  4838.2 2043.59  4846.6 2041.99  4891.3 2037.16  4896.9 2037.32  4905.3 2035.81
  4913.7 2035.48  4919.3 2034.68  4927.7 2035.73  4941.6 2035.19    4964 2035.38
  4980.8 2033.84  4997.3 2033.36  5004.8 2031.23  5012.8 2031.23    5013 2030.73
  5016.5 2030.73  5016.8 2031.23  5024.8 2031.54  5034.8  2036.1  5044.8 2041.93
  5054.8 2046.86  5064.8 2049.52  5084.8 2051.75  5092.3 2052.97  5094.8 2052.97
#Mann= 3 ,-1 , 0
  4771.1     .07       0  5012.8     .05       0  5016.8     .07       0
Bank Sta=5012.8,5016.8
XS Rating Curve= 0 ,0
Exp/Cntr=0.3,0.1

Type RM Length L Ch R = 1 ,18170   ,454,454,454
BEGIN DESCRIPTION:
Dry Creek 38.0
END DESCRIPTION:
XS GIS Cut Line= 3
      1828874.96       13922125.        1829075.       13922125.
      1829375.03     13922024.99
#Sta/Elev= 30
  4793.8 2052.66  4803.8 2051.91  4823.8 2048.69  4833.8 2046.32  4883.8 2032.07
  4903.8 2029.47  4923.8 2028.68  4953.8 2030.59  4983.8 2028.91  5004.4 2029.34
  5012.9 2027.07  5013.2 2026.57  5016.7 2026.57  5016.9 2027.07  5025.5 2028.49
    5036 2028.22  5046.5 2029.31  5057.1 2029.33  5067.6 2033.17  5072.9 2036.76
  5078.2 2036.76  5088.7 2039.91  5120.3 2047.49  5141.4 2050.88  5194.1  2057.1
  5215.2 2058.35  5236.3 2060.81  5257.4 2064.74  5307.4 2078.44  5310.1 2078.44
#Mann= 3 ,-1 , 0
  4793.8     .07       0  5012.9     .05       0  5016.9     .07       0
Bank Sta=5012.9,5016.9
XS Rating Curve= 0 ,0
Exp/Cntr=0.3,0.1

Type RM Length L Ch R = 1 ,17716   ,438,438,438
BEGIN DESCRIPTION:
Dry Creek 37.0
END DESCRIPTION:
XS GIS Cut Line= 3
        1828975.       13922575.        1829025.       13922525.
      1829324.98     13922275.01
#Sta/Elev= 30
  4925.1 2047.35  4928.6 2047.35  4953.4 2042.68  4981.7 2033.54  4992.3 2028.69
  4999.1 2028.69    5003 2023.56  5009.5 2021.03  5015.3 2020.98  5015.5 2020.48
  5019.3 2020.98  5038.1 2022.21  5052.4 2022.04  5060.2 2024.52  5066.8 2023.83
  5073.9 2025.11  5087.6 2025.51  5095.4 2026.59  5144.9 2027.02    5152 2027.91
  5179.8 2027.63  5187.8 2026.98  5194.3 2027.87  5202.1 2029.88  5208.6 2030.32
  5251.6 2037.85  5301.1 2044.63  5329.7 2050.26  5362.5  2054.4  5386.3 2056.35
#Mann= 5 ,-1 , 0
  4925.1     .07       0  5015.3     .05       0  5019.3     .07       0
  5179.8      .1       0  5362.5     .07       0
Bank Sta=5015.3,5019.3
XS Rating Curve= 0 ,0
Exp/Cntr=0.3,0.1

Type RM Length L Ch R = 1 ,17278   ,475,475,475
BEGIN DESCRIPTION:
Dry Creek 36.0
END DESCRIPTION:
XS GIS Cut Line= 3
        1829025.       13922775.        1829275.       13922875.
      1829525.04       13922875.
#Sta/Elev= 30
  4737.5 2039.62  4776.5 2038.58  4823.7 2035.24    4860 2031.77  4866.7 2030.25
  4889.6 2028.47  4908.5 2025.46  4913.9 2025.94  4931.4 2022.19  4938.1 2019.95
  4943.5 2020.71  4952.9 2018.86  4962.3 2017.79  5014.8 2017.36    5015 2016.86
  5018.5 2016.86  5018.8 2017.36  5046.8  2020.7  5096.8 2022.18  5116.8 2025.65
  5136.8 2032.01  5146.8 2035.74  5166.8 2043.99  5186.8 2053.13    5195 2055.75
  5206.8 2060.34  5216.8 2065.79  5226.8 2080.49  5236.8 2086.35  5256.8 2089.18
#Mann= 4 ,-1 , 0
  4737.5     .07       0  5014.8     .05       0  5018.8     .07       0
    5195      .1       0
Bank Sta=5014.8,5018.8
XS Rating Curve= 0 ,0
Exp/Cntr=0.3,0.1

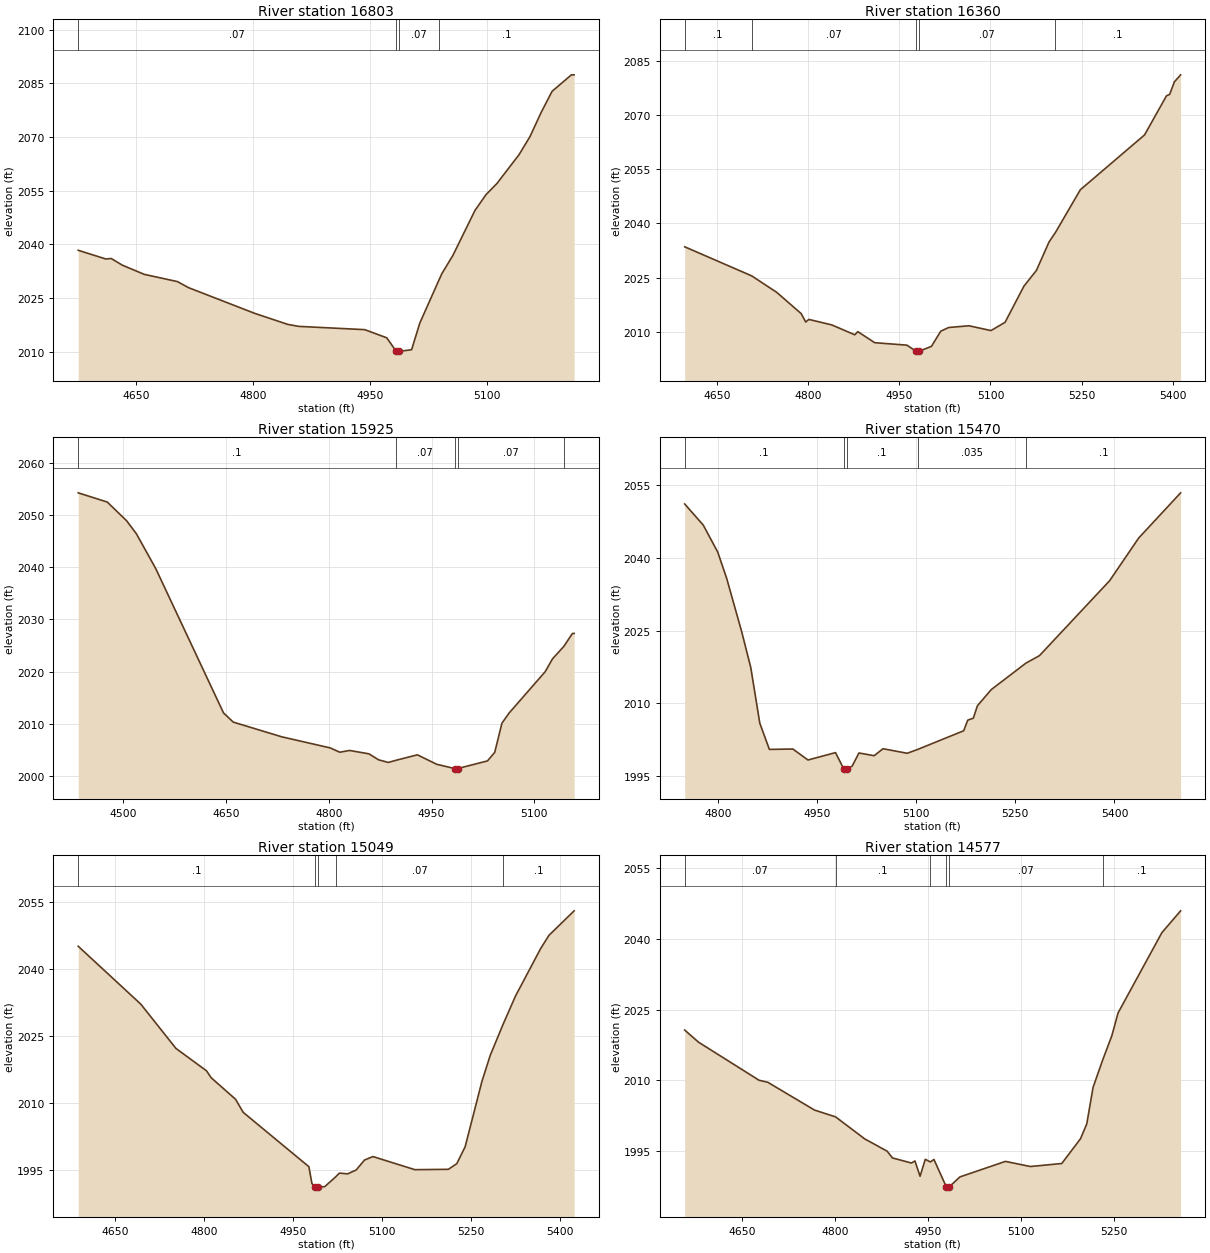
Type RM Length L Ch R = 1 ,16803   ,443,443,443
BEGIN DESCRIPTION:
Dry Creek 35.0
END DESCRIPTION:
XS GIS Cut Line= 3
        1828875.       13922975.        1829175.       13923275.
      1829325.01     13923425.01
#Sta/Elev= 30
  4575.7 2038.32  4611.1 2035.89  4618.1 2036.02  4632.3 2034.16  4660.5 2031.59
    4703 2029.57  4717.1 2027.89    4802 2020.71  4844.4 2017.62  4858.5 2017.06
  4943.4 2016.14  4971.7 2013.85  4983.8 2010.08  4984.1 2009.58  4987.6 2009.58
  4987.8 2010.08  5003.5 2010.53  5014.1 2018.01  5038.1 2029.74  5042.4 2031.81
  5056.5 2036.89  5084.8 2049.44    5099 2053.87  5113.1 2057.01  5141.4 2065.04
  5155.5 2070.12  5169.7 2076.82  5183.8 2082.75  5208.6 2087.35  5212.1 2087.35
#Mann= 4 ,-1 , 0
  4575.7     .07       0  4983.8     .05       0  4987.8     .07       0
  5038.1      .1       0
Bank Sta=4983.8,4987.8
XS Rating Curve= 0 ,0
Exp/Cntr=0.3,0.1

Type RM Length L Ch R = 1 ,16360   ,435,435,435
BEGIN DESCRIPTION:
Dry Creek 34.0
END DESCRIPTION:
XS GIS Cut Line= 3
        1828775.       13923125.        1828825.       13923525.
      1829224.98       13923625.
#Sta/Elev= 30
  4597.2 2033.51  4707.4 2025.46  4748.4 2020.92  4788.7 2015.03  4796.2 2012.69
  4801.3 2013.41  4839.1 2011.89  4876.9 2009.15  4881.9 2010.02  4909.6 2006.97
  4962.5 2006.29  4977.9 2004.58  4978.2 2004.08  4982.5 2004.58  5002.9 2005.95
  5018.3 2010.16  5031.2 2011.17  5064.7 2011.65  5100.8 2010.32    5124 2012.61
  5154.9 2022.59  5175.5 2026.97  5196.2 2034.82  5206.8 2037.47  5247.7 2049.29
  5353.3 2064.47  5389.4  2075.3  5394.6 2075.69  5402.3 2079.14  5412.6  2081.1
#Mann= 5 ,-1 , 0
  4597.2      .1       0  4707.4     .07       0  4977.9     .05       0
  4982.5     .07       0  5206.8      .1       0
Bank Sta=4977.9,4982.5
XS Rating Curve= 0 ,0
Exp/Cntr=0.3,0.1

Type RM Length L Ch R = 1 ,15925   ,455,455,455
BEGIN DESCRIPTION:
Dry Creek 33.0
END DESCRIPTION:
XS GIS Cut Line= 3
      1828324.99     13924325.01        1828725.       13923925.
      1828874.99       13923875.
#Sta/Elev= 30
  4434.3 2054.31  4476.7 2052.54    4505 2048.94  4519.2 2046.45  4547.4 2039.78
  4646.4 2012.05  4660.6 2010.29  4731.3 2007.47    4802 2005.34  4816.1 2004.51
  4830.3 2004.85  4858.6  2004.2  4872.7 2003.05  4886.9 2002.55  4898.1 2002.96
  4929.3 2004.01  4957.6 2002.19  4983.6 2001.38  4983.9 2000.88  4987.9 2000.88
  4988.2 2001.38  5031.6 2002.84  5042.2 2004.49  5052.7 2010.08  5063.2 2012.04
  5115.9 2019.98  5126.5 2022.43  5143.2 2024.85  5155.5 2027.31  5158.1 2027.31
#Mann= 5 ,-1 , 0
  4434.3      .1       0  4898.1     .07       0  4983.6     .05       0
  4988.2     .07       0  5143.2      .1       0
Bank Sta=4983.6,4988.2
XS Rating Curve= 0 ,0
Exp/Cntr=0.3,0.1

Type RM Length L Ch R = 1 ,15470   ,421,421,421
BEGIN DESCRIPTION:
Dry Creek 32.0
END DESCRIPTION:
XS GIS Cut Line= 3
      1828574.99     13924475.01        1828775.       13924325.
      1829174.99     13924025.01
#Sta/Elev= 30
    4750 2051.17  4778.1  2046.8    4800 2041.22  4813.6 2035.75  4836.5 2024.62
    4850 2017.33  4863.6 2005.86  4878.1 2000.43  4913.6 2000.51  4936.5 1998.24
  4978.1 1999.77  4990.4 1996.44  4990.7 1995.94  4995.1 1996.44  5003.1 1996.94
  5013.6 1999.69  5036.5 1999.13    5050 2000.57  5086.5 1999.63  5102.3 2000.42
  5171.9 2004.28  5178.1 2006.48  5186.5 2006.88  5192.7 2009.45  5213.6 2012.79
    5266 2018.26  5286.5 2019.81  5392.7 2035.31  5436.5 2044.11    5500 2053.47
#Mann= 5 ,-1 , 0
    4750      .1       0  4990.4     .05       0  4995.1      .1       0
  5102.3    .035       0    5266      .1       0
Bank Sta=4990.4,4995.1
XS Rating Curve= 0 ,0
Exp/Cntr=0.3,0.1

Type RM Length L Ch R = 1 ,15049   ,472,472,472
BEGIN DESCRIPTION:
Dry Creek 31.0
END DESCRIPTION:
XS GIS Cut Line= 3
      1828675.01       13924675.        1829075.       13924575.
      1829375.03     13924274.97
#Sta/Elev= 30
  4587.7 2045.12  4693.3 2032.17  4752.6 2022.27  4804.2 2017.26  4811.9 2015.73
  4853.1 2010.91    4866 2007.98  4976.8 1995.83    4982 1992.04  4987.3 1991.31
  4987.7 1990.81    4992 1991.31  5003.5 1991.36  5022.1 1993.56  5028.3 1994.39
  5042.4 1994.23  5056.6 1995.09  5070.7 1997.32  5084.9 1998.09  5155.6 1995.16
  5212.1 1995.24  5226.3  1996.5  5240.4 2000.27  5268.7 2014.89  5282.8 2020.75
  5304.7 2027.75  5325.3 2033.97  5367.7 2044.58  5381.8 2047.56  5424.3 2053.04
#Mann= 5 ,-1 , 0
  4587.7      .1       0  4987.3     .05       0    4992      .1       0
  5022.1     .07       0  5304.7      .1       0
Bank Sta=4987.3,4992
XS Rating Curve= 0 ,0
Exp/Cntr=0.3,0.1

Type RM Length L Ch R = 1 ,14577   ,435,435,435
BEGIN DESCRIPTION:
Dry Creek 30.0
END DESCRIPTION:
XS GIS Cut Line= 3
      1829274.99     13925175.02        1829475.       13924775.
        1829525.     13924424.98
#Sta/Elev= 30
    4557 2020.66  4579.4 2018.08  4677.2 2009.99  4691.2 2009.57  4766.6 2003.67
  4800.7 2002.22  4847.7 1997.55    4884 1994.93  4892.4 1993.51  4923.2 1992.42
  4928.8 1992.86  4937.1 1989.61  4945.5 1993.21  4953.7 1992.65  4959.5 1993.18
  4979.4 1987.38  4979.8 1986.88  4984.4 1987.38  5001.4 1989.47  5074.9 1992.77
  5115.3 1991.68  5165.9 1992.32  5196.2 1997.59  5206.3 2000.75  5216.4 2008.47
  5231.7 2014.21  5246.7 2019.44  5256.8 2024.29  5327.5 2041.33  5357.8 2045.97
#Mann= 6 ,-1 , 0
    4557     .07       0  4800.7      .1       0  4953.7     .07       0
  4979.4     .05       0  4984.4     .07       0  5231.7      .1       0
Bank Sta=4979.4,4984.4
XS Rating Curve= 0 ,0
Exp/Cntr=0.3,0.1

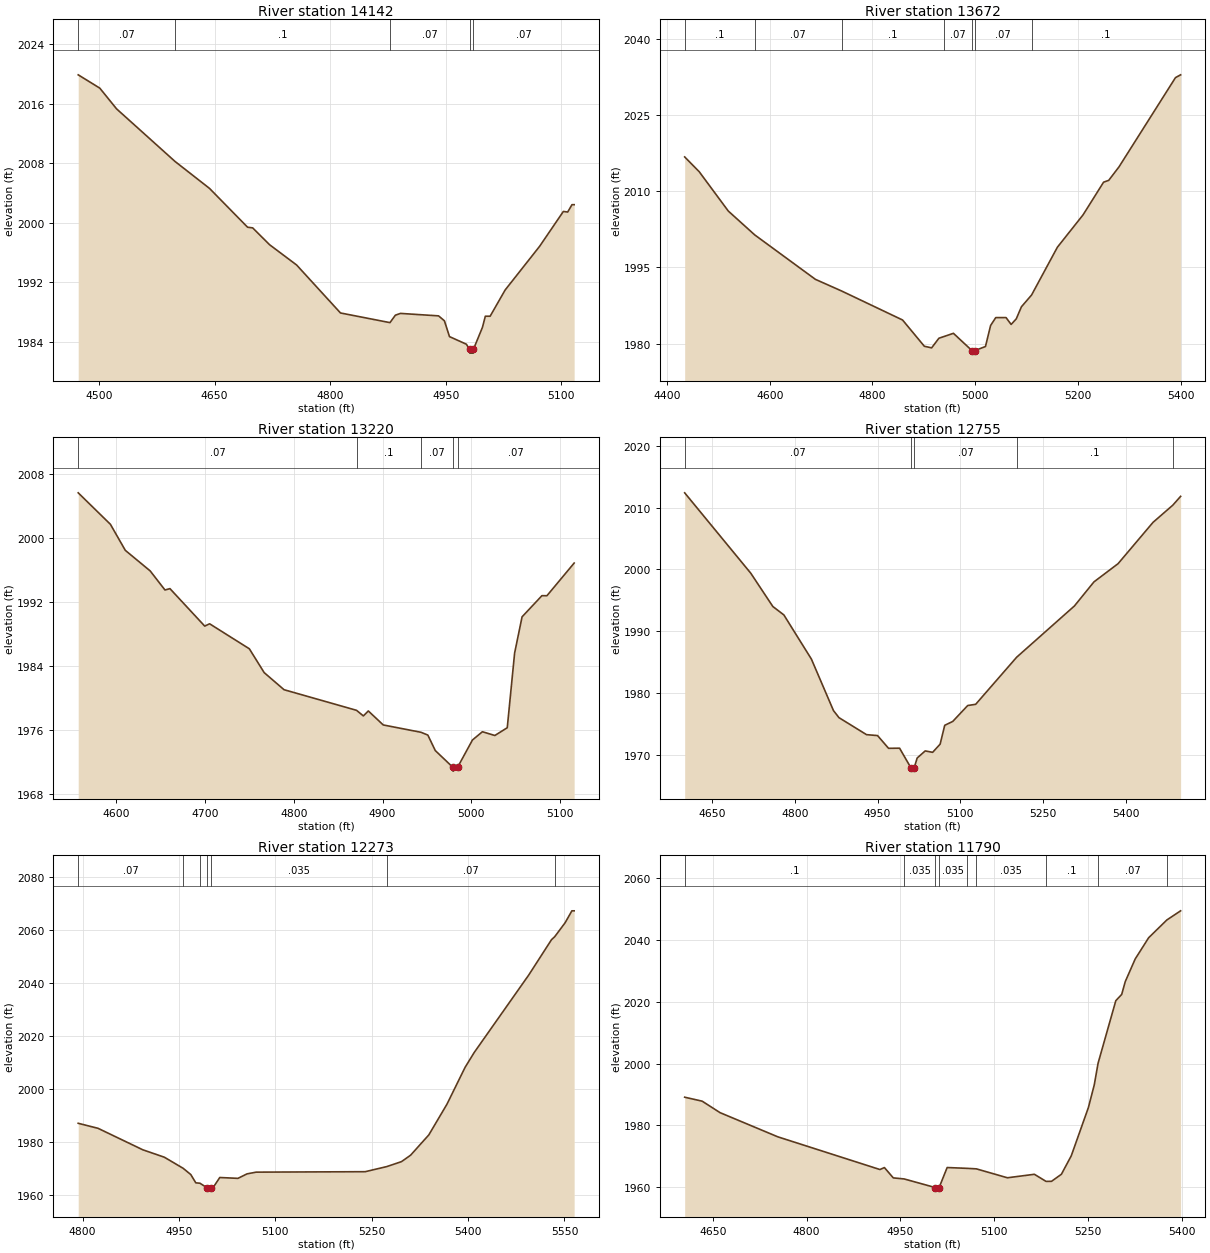
Type RM Length L Ch R = 1 ,14142   ,470,470,470
BEGIN DESCRIPTION:
Dry Creek 29.0
END DESCRIPTION:
XS GIS Cut Line= 3
      1829475.03     13925324.97        1829825.       13924925.
      1829875.01     13924824.97
#Sta/Elev= 30
  4473.2 2019.87  4501.2 2018.08    4523 2015.29  4598.7 2008.23  4643.5  2004.6
  4692.9 1999.38  4699.5 1999.29  4721.4 1997.03  4756.5  1994.3  4813.4 1987.85
  4877.6 1986.55  4884.6 1987.55  4891.2 1987.79  4940.6 1987.46  4948.2  1986.8
  4954.8 1984.67  4976.7 1983.65  4980.8 1982.95  4981.2 1982.45  4985.5 1982.45
  4985.8 1982.95  4997.5  1985.9  5001.3 1987.41  5007.5 1987.41    5027 1990.94
  5071.7 1996.81  5102.5  2001.5  5108.1 2001.42  5113.7 2002.41  5116.5 2002.41
#Mann= 5 ,-1 , 0
  4473.2     .07       0  4598.7      .1       0  4877.6     .07       0
  4980.8     .05       0  4985.8     .07       0
Bank Sta=4980.8,4985.8
XS Rating Curve= 0 ,0
Exp/Cntr=0.3,0.1

Type RM Length L Ch R = 1 ,13672   ,452,452,452
BEGIN DESCRIPTION:
Dry Creek 28.0
END DESCRIPTION:
XS GIS Cut Line= 3
      1829724.98     13925675.02        1830125.       13925275.
      1830524.99       13925275.
#Sta/Elev= 30
  4434.3 2016.73  4462.6 2013.82  4519.2 2006.08  4570.6 2001.39  4688.9 1992.63
  4740.3 1990.32  4858.6 1984.63    4901 1979.46  4915.2 1979.15  4929.3 1981.04
  4939.3 1981.38  4957.6 1982.01  4993.7 1978.61  4994.2 1978.11  4999.2 1978.61
    5020 1979.41    5030 1983.55    5040  1985.1    5060 1985.11    5070 1983.76
    5080 1984.86    5090 1987.23  5109.8 1989.55    5160 1998.95    5210 2005.32
    5250 2011.76    5260 2012.12    5280 2014.77    5390 2032.34    5400 2032.89
#Mann= 7 ,-1 , 0
  4434.3      .1       0  4570.6     .07       0  4740.3      .1       0
  4939.3     .07       0  4993.7     .05       0  4999.2     .07       0
  5109.8      .1       0
Bank Sta=4993.7,4999.2
XS Rating Curve= 0 ,0
Exp/Cntr=0.3,0.1

Type RM Length L Ch R = 1 ,13220   ,465,465,465
BEGIN DESCRIPTION:
Dry Creek 27.0
END DESCRIPTION:
XS GIS Cut Line= 3
      1829874.99       13925875.        1830275.       13925675.
      1830374.98     13925625.01
#Sta/Elev= 30
  4556.9 2005.69  4593.2 2001.75    4610 1998.49    4638 1995.92  4654.7 1993.53
  4660.3  1993.7  4699.5 1989.01    4705  1989.3  4749.8 1986.17  4766.5 1983.19
  4788.9 1981.05  4870.6 1978.47  4878.3 1977.77  4883.9 1978.39  4900.7 1976.64
  4943.3 1975.72    4951 1975.37  4959.4 1973.43    4979 1971.36  4979.4 1970.86
  4984.6 1971.36  5001.3 1974.76  5012.5 1975.79  5026.5 1975.32  5040.5 1976.29
  5048.8 1985.64  5057.2 1990.17  5079.6 1992.82  5085.2 1992.81  5115.9  1996.9
#Mann= 5 ,-1 , 0
  4556.9     .07       0  4870.6      .1       0  4943.3     .07       0
    4979     .05       0  4984.6     .07       0
Bank Sta=4979,4984.6
XS Rating Curve= 0 ,0
Exp/Cntr=0.3,0.1

Type RM Length L Ch R = 1 ,12755   ,482,482,482
BEGIN DESCRIPTION:
Dry Creek 26.0
END DESCRIPTION:
XS GIS Cut Line= 3
      1829824.99       13926125.        1830225.       13926125.
      1830624.99     13925825.01
#Sta/Elev= 30
    4600  2012.4    4720 1999.39    4760 1994.01    4780 1992.65    4830  1985.5
    4870 1977.18    4880 1976.03    4930 1973.28    4950 1973.13    4970 1971.07
    4990 1971.09  5010.8 1967.88  5011.2 1967.38  5015.9 1967.38  5016.4 1967.88
  5021.9  1969.5  5036.5 1970.65    5050 1970.42  5063.6 1971.75  5071.9 1974.79
  5086.5 1975.42  5113.6 1977.99  5128.1 1978.19  5202.5 1985.81  5307.3  1994.1
  5342.7 1997.99  5386.5 2000.94    5450 2007.63  5485.8  2010.4    5500 2011.83
#Mann= 5 ,-1 , 0
    4600     .07       0  5010.8     .05       0  5016.4     .07       0
  5202.5      .1       0  5485.8     .07       0
Bank Sta=5010.8,5016.4
XS Rating Curve= 0 ,0
Exp/Cntr=0.3,0.1

Type RM Length L Ch R = 1 ,12273   ,483,483,483
BEGIN DESCRIPTION:
Dry Creek 25.0
END DESCRIPTION:
XS GIS Cut Line= 3
        1830025.       13926525.        1830225.       13926575.
      1830624.97     13926974.97
#Sta/Elev= 30
  4793.3 1986.98  4824.2 1985.08  4893.8 1976.99  4927.3  1974.2  4956.6 1970.01
  4968.5 1967.65  4976.3 1964.53  4982.7 1964.39  4993.9 1962.66  4994.4 1962.16
  4999.9 1962.66    5003 1962.66  5013.6 1966.54  5041.9 1966.22    5056 1967.91
  5070.2 1968.56  5239.9 1968.73  5273.4 1970.65  5296.4 1972.52  5310.6 1974.96
  5338.9 1982.59  5367.2 1994.19  5395.4 2008.08  5409.6 2013.68  5494.4 2042.86
  5529.8 2056.17  5534.9 2057.33    5551 2062.56  5561.6 2067.07  5565.1 2067.07
#Mann= 7 ,-1 , 0
  4793.3     .07       0  4956.6      .1       0  4982.7    .035       0
  4993.9    .035       0  4999.9    .035       0  5273.4     .07       0
  5534.9      .1       0
Bank Sta=4993.9,4999.9
XS Rating Curve= 0 ,0
Exp/Cntr=0.3,0.1

Type RM Length L Ch R = 1 ,11790   ,472,472,472
BEGIN DESCRIPTION:
Dry Creek 24.0
END DESCRIPTION:
XS GIS Cut Line= 3
      1829824.97     13926774.97        1830125.       13927025.
      1830475.03     13927225.01
#Sta/Elev= 30
  4604.8  1989.1  4632.8 1987.81  4661.5 1984.08  4753.9 1976.25  4917.3 1965.65
  4924.4 1966.29  4938.7 1962.94  4956.1  1962.6    5006  1959.8  5006.5  1959.3
    5012  1959.8  5024.9  1966.3  5056.3 1966.04  5071.6 1965.87  5121.3 1962.98
  5164.5 1964.11  5183.1 1961.81  5191.9 1961.83  5207.7 1964.12  5223.5  1970.1
  5250.9 1985.74  5260.3 1993.09  5266.4 2000.11  5294.8 2020.39  5304.2 2022.41
  5309.9 2026.56  5325.8  2033.9  5347.4  2040.8  5376.5 2046.55  5398.5 2049.51
#Mann= 9 ,-1 , 0
  4604.8      .1       0  4956.1    .035       0    5006    .035       0
    5012    .035       0  5056.3     .07       0  5071.6    .035       0
  5183.1      .1       0  5266.4     .07       0  5376.5      .1       0
Bank Sta=5006,5012
XS Rating Curve= 0 ,0
Exp/Cntr=0.3,0.1