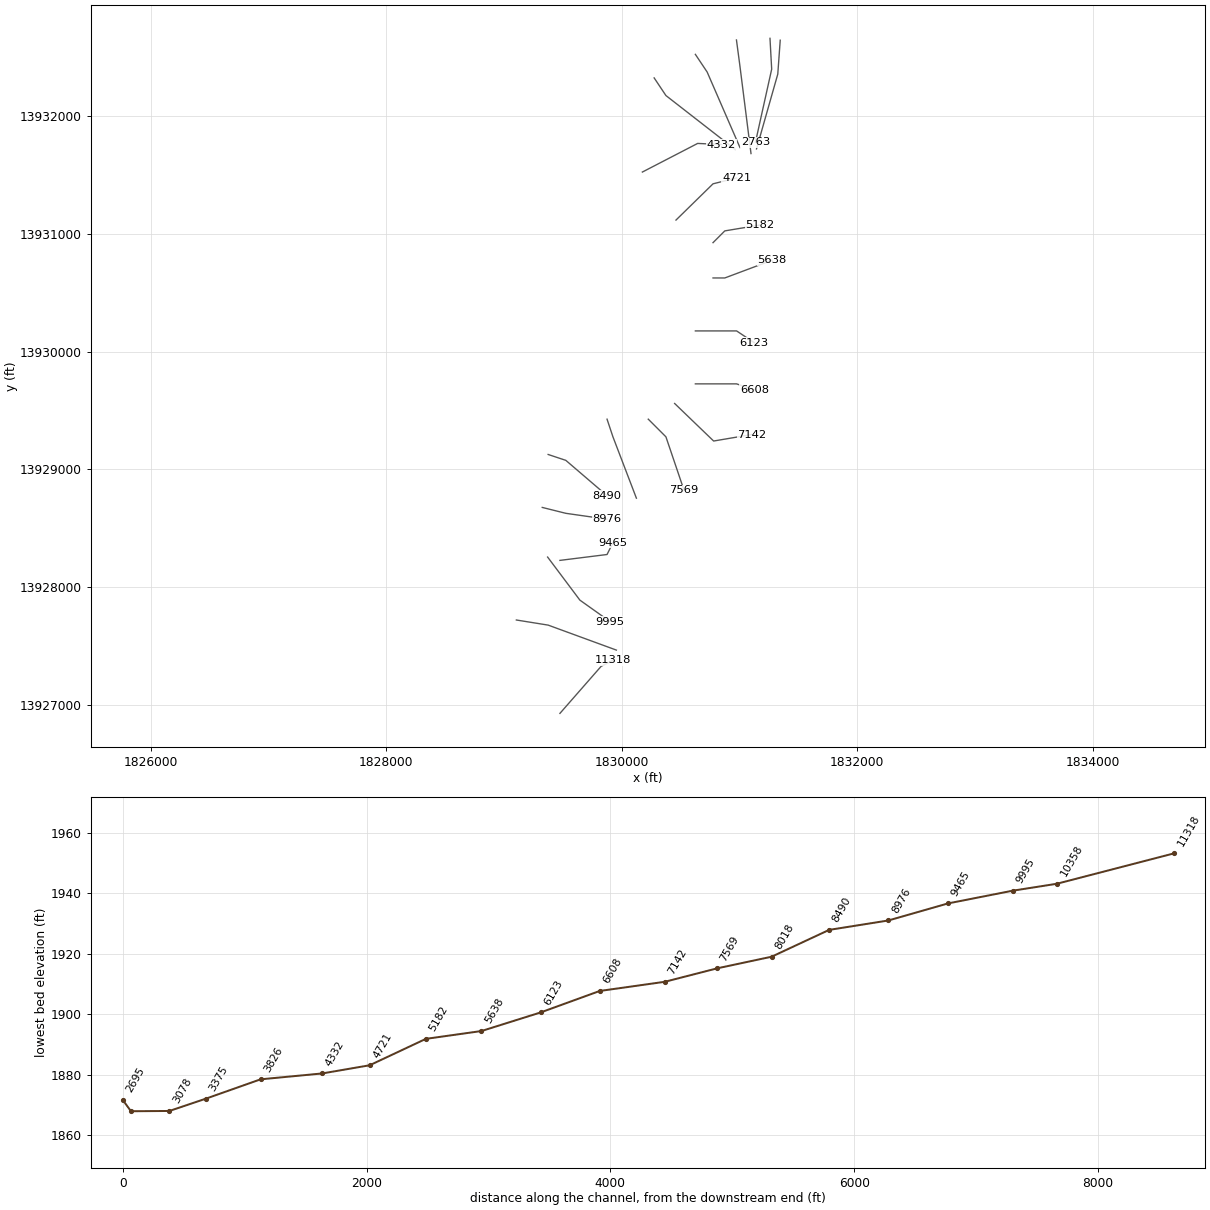
HEC-RAS study Dry Creek.prj: Dry Creek Base Level Engineering

--- Dry Creek.g01 (geometry) --- (continued)

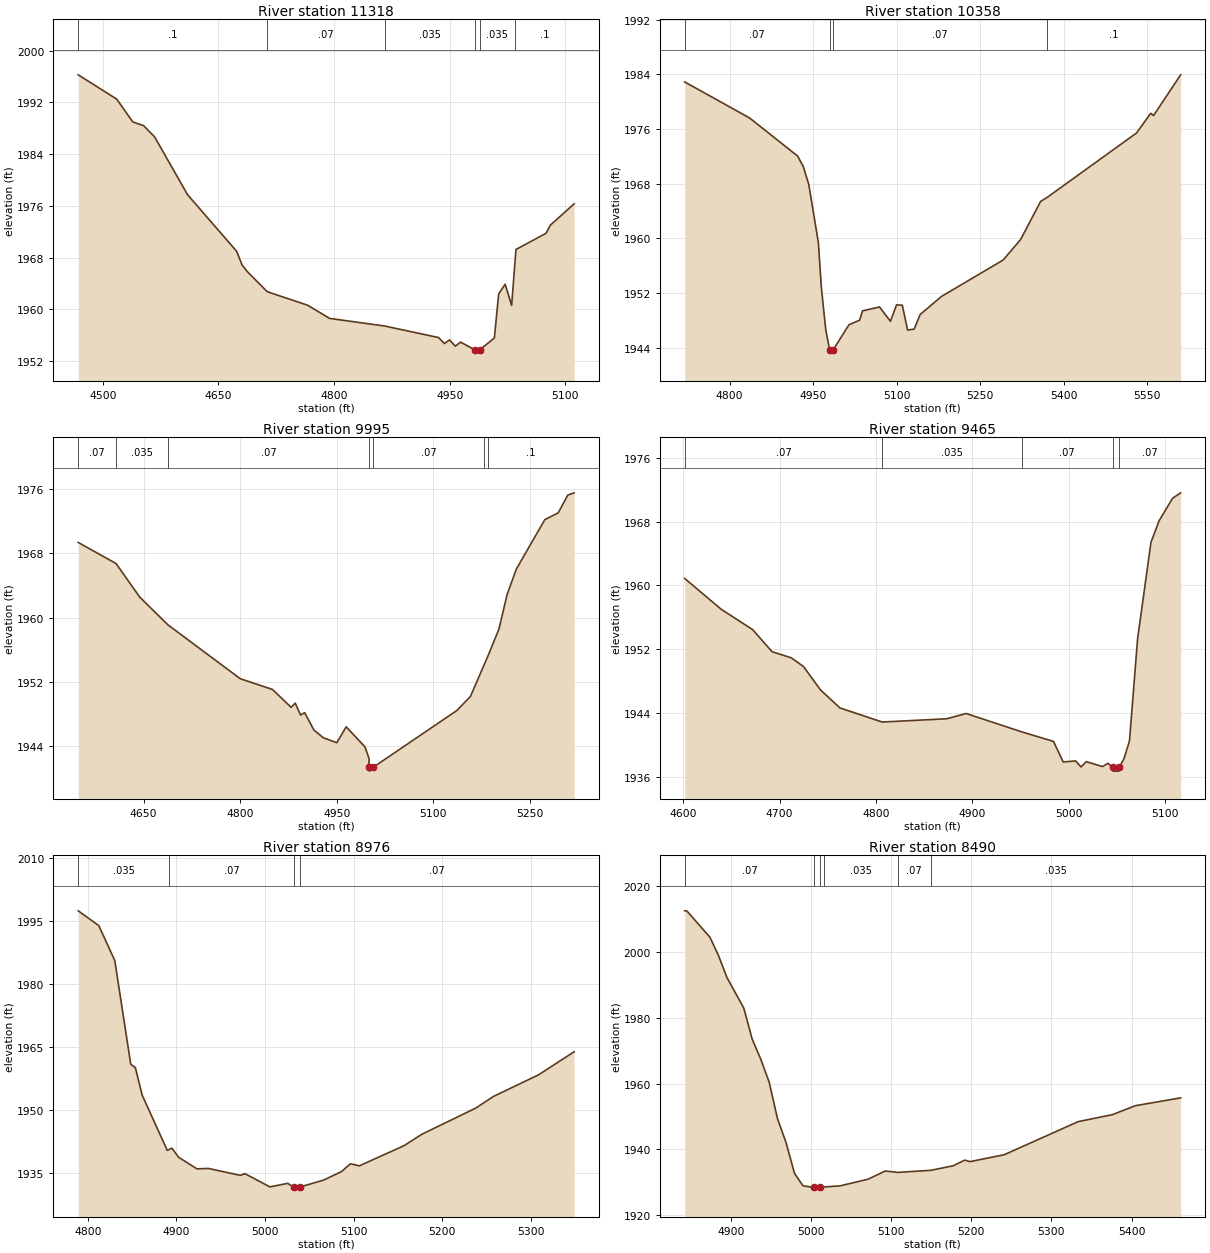
Type RM Length L Ch R = 1 ,11318   ,960,960,960
BEGIN DESCRIPTION:
Dry Creek 23.0
END DESCRIPTION:
XS GIS Cut Line= 3
      1829474.97     13926924.97        1829825.       13927325.
      1829925.04     13927375.02
#Sta/Elev= 30
  4468.1 1996.27    4518 1992.52  4538.9 1988.99  4553.1  1988.4  4567.3 1986.66
    4610 1977.73  4673.6 1968.99  4680.7 1966.88  4687.9 1965.79  4713.3 1962.74
  4765.7 1960.65  4794.2 1958.61  4866.2 1957.42  4935.6 1955.65  4943.2 1954.72
  4949.8 1955.28  4957.4 1954.32  4964.1 1954.94  4982.9 1953.74  4983.4 1953.24
  4988.9 1953.74    5008 1955.58  5013.6 1962.41    5022 1963.89  5030.4 1960.62
  5034.8 1967.41    5036 1969.26  5075.1 1971.78  5080.7 1973.04  5111.5 1976.32
#Mann= 6 ,-1 , 0
  4468.1      .1       0  4713.3     .07       0  4866.2    .035       0
  4982.9    .035       0  4988.9    .035       0  5034.8      .1       0
Bank Sta=4982.9,4988.9
XS Rating Curve= 0 ,0
Exp/Cntr=0.3,0.1

Type RM Length L Ch R = 1 ,10358   ,363,363,363
BEGIN DESCRIPTION:
Dry Creek 22.0
END DESCRIPTION:
XS GIS Cut Line= 3
       1829104.9     13927718.46        1829375.       13927675.
      1829954.06     13927462.79
#Sta/Elev= 30
  4719.4 1982.91  4835.8 1977.64  4922.1 1972.06  4932.2 1970.54  4942.3 1967.86
  4959.5 1959.32  4964.6 1952.96  4972.7 1946.57  4979.6 1943.69  4980.1 1943.19
  4986.1 1943.69  5014.3 1947.34  5033.4 1948.01  5038.7 1949.38  5069.2 1949.95
  5088.8 1947.85  5099.7 1950.26  5110.1 1950.21  5119.6 1946.57  5131.4 1946.71
  5142.1 1948.85  5180.6  1951.5  5291.2 1956.83  5322.5 1959.83  5358.3  1965.4
  5370.5 1966.02  5530.7 1975.44  5555.9 1978.31  5561.2 1977.99  5609.7 1983.95
#Mann= 4 ,-1 , 0
  4719.4     .07       0  4979.6     .05       0  4986.1     .07       0
  5370.5      .1       0
Bank Sta=4979.6,4986.1
XS Rating Curve= 0 ,0
Exp/Cntr=0.3,0.1

Type RM Length L Ch R = 1 ,9995    ,530,530,530
BEGIN DESCRIPTION:
Dry Creek 21.0
END DESCRIPTION:
XS GIS Cut Line= 3
      1829370.36     13928253.33      1829644.26     13927887.39
       1829899.9     13927705.55
#Sta/Elev= 30
  4548.3 1969.36  4607.1 1966.74  4643.9 1962.56  4687.8  1959.1  4800.1  1952.4
  4850.2 1951.06  4879.3 1948.83  4885.6 1949.36  4893.9 1947.87  4900.2 1948.17
  4914.8 1945.99  4929.4 1945.04  4950.2 1944.43  4964.8 1946.41    4994 1943.91
  5000.2 1942.49  5000.3 1941.39  5000.8 1940.89  5007.2 1941.39    5137 1948.45
  5157.9 1950.19  5178.5    1954  5184.7 1955.14  5202.2 1958.57  5214.9 1962.87
  5229.2 1966.04  5273.5  1972.2  5294.4 1973.05  5309.2 1975.26  5319.1 1975.54
#Mann= 7 ,-1 , 0
  4548.3     .07       0  4607.1    .035       0  4687.8     .07       0
  5000.3     .05       0  5007.2     .07       0  5178.5     .07       0
  5184.7      .1       0
Bank Sta=5000.3,5007.2
XS Rating Curve= 0 ,0
Exp/Cntr=0.3,0.1

Type RM Length L Ch R = 1 ,9465    ,489,489,489
BEGIN DESCRIPTION:
Dry Creek 20.0
END DESCRIPTION:
XS GIS Cut Line= 3
      1829475.04     13928225.01        1829875.       13928275.
      1829925.01     13928375.02
#Sta/Elev= 30
  4601.4 1960.86  4639.2    1957  4671.9 1954.44  4692.1 1951.67  4712.2 1950.89
  4724.8  1949.8  4742.4 1946.87  4762.6 1944.61  4806.5 1942.84  4873.5 1943.25
  4893.6 1943.91  4951.3 1941.61  4984.3 1940.41  4994.4 1937.83  5007.3 1937.96
  5012.9 1937.21  5018.4 1937.87  5035.2 1937.25  5040.8 1937.67  5045.6 1937.18
  5046.1 1936.68  5052.2 1936.68  5052.7 1937.18  5057.6 1938.27  5063.2 1940.46
  5071.6 1953.24  5085.5 1965.38  5093.9 1968.08  5107.9 1970.91  5116.3  1971.6
#Mann= 5 ,-1 , 0
  4601.4     .07       0  4806.5    .035       0  4951.3     .07       0
  5045.6     .05       0  5052.7     .07       0
Bank Sta=5045.6,5052.7
XS Rating Curve= 0 ,0
Exp/Cntr=0.3,0.1

Type RM Length L Ch R = 1 ,8976    ,486,486,486
BEGIN DESCRIPTION:
Dry Creek 19.0
END DESCRIPTION:
XS GIS Cut Line= 3
      1829324.97     13928675.01        1829525.       13928625.
      1829874.96     13928575.01
#Sta/Elev= 30
  4789.1 1997.39  4812.3 1993.87  4830.4 1985.53  4848.4 1960.81  4853.6 1960.01
  4861.3 1953.44  4889.6 1940.28  4891.8  1940.5  4894.8 1940.81  4902.5 1938.62
  4923.1 1935.87    4936 1935.97  4972.1 1934.32  4977.2 1934.73  5005.4 1931.58
  5025.6 1932.42  5032.1 1931.54  5032.6 1931.04  5038.8 1931.04  5039.3 1931.54
    5066 1933.19  5086.2 1935.22  5096.3 1937.08  5106.4 1936.59  5156.9 1941.41
  5177.1 1944.14  5237.7 1950.35  5257.9 1953.16  5308.4 1958.26  5348.8 1963.79
#Mann= 4 ,-1 , 0
  4789.1    .035       0  4891.8     .07       0  5032.1     .05       0
  5039.3     .07       0
Bank Sta=5032.1,5039.3
XS Rating Curve= 0 ,0
Exp/Cntr=0.3,0.1

Type RM Length L Ch R = 1 ,8490    ,472,472,472
BEGIN DESCRIPTION:
Dry Creek 18.0
END DESCRIPTION:
XS GIS Cut Line= 3
      1829375.02     13929124.99        1829525.       13929075.
      1829875.02     13928774.98
#Sta/Elev= 30
  4842.2 2012.56  4844.8 2012.56  4873.8 2004.51  4884.3 1999.03  4894.9 1992.32
    4916 1982.97  4926.5 1973.52    4937 1967.55  4947.6 1960.53  4958.1 1949.33
  4968.7 1942.12  4979.2 1932.78  4989.8 1928.95  5003.8 1928.42  5004.3 1927.92
    5011 1928.42  5015.9 1928.59    5036  1928.9  5071.1 1930.93  5092.5 1933.42
  5108.3 1933.01  5149.4 1933.64  5177.5 1935.03  5191.8 1936.74  5198.4 1936.28
  5241.2 1938.39  5333.4 1948.45  5376.2 1950.57  5404.7 1953.29  5461.3 1955.67
#Mann= 6 ,-1 , 0
  4842.2     .07       0  5003.8     .05       0    5011     .07       0
  5015.9    .035       0  5108.3     .07       0  5149.4    .035       0
Bank Sta=5003.8,5011
XS Rating Curve= 0 ,0
Exp/Cntr=0.3,0.1

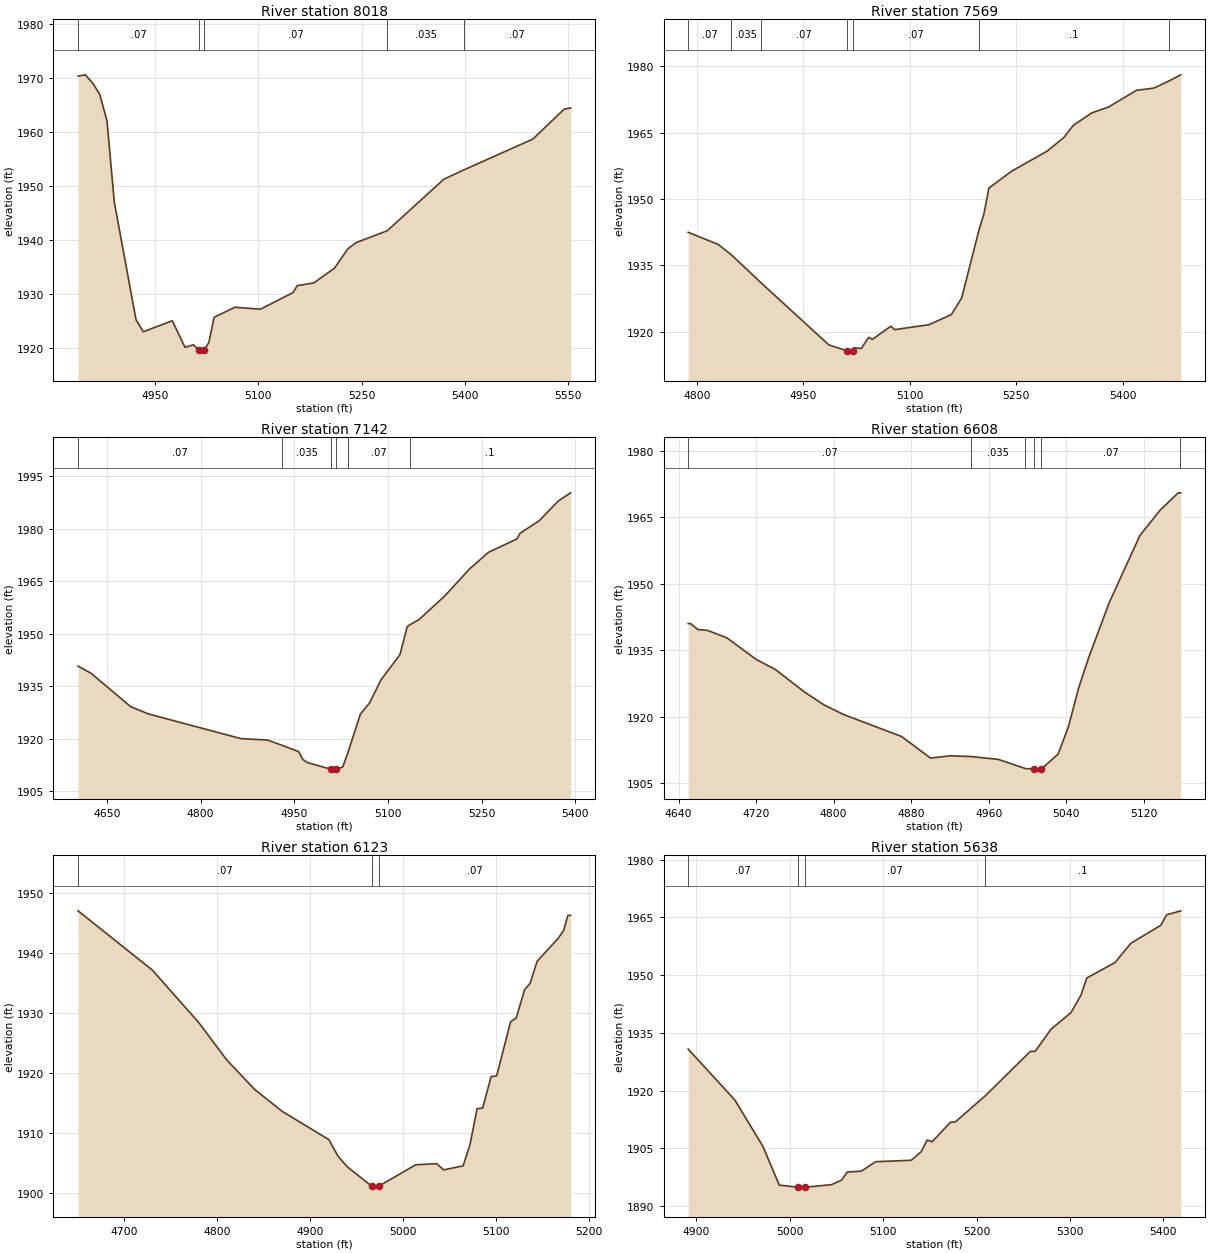
Type RM Length L Ch R = 1 ,8018    ,449,449,449
BEGIN DESCRIPTION:
Dry Creek 17.0
END DESCRIPTION:
XS GIS Cut Line= 3
      1829875.01     13929424.98        1829925.       13929275.
      1830124.26     13928753.68
#Sta/Elev= 30
  4837.8 1970.28  4848.3 1970.51  4858.9 1969.02  4869.4  1966.9  4879.9 1961.97
  4890.5 1946.99  4922.1 1925.21  4932.7 1922.99  4974.8 1925.03  4993.3 1920.12
  5005.6 1920.58  5013.7 1919.54  5014.2 1919.04  5020.9 1919.54    5028    1921
  5035.6 1925.66  5065.7 1927.52    5103 1927.17  5150.5 1930.24  5156.5 1931.52
  5180.6 1932.02  5210.7 1934.76    5230 1938.32  5242.1 1939.47  5287.4 1941.68
  5369.6  1951.2  5398.8 1952.93  5499.1 1958.63  5544.7 1964.17    5554 1964.39
#Mann= 5 ,-1 , 0
  4837.8     .07       0  5013.7     .05       0  5020.9     .07       0
  5287.4    .035       0  5398.8     .07       0
Bank Sta=5013.7,5020.9
XS Rating Curve= 0 ,0
Exp/Cntr=0.3,0.1

Type RM Length L Ch R = 1 ,7569    ,427,427,427
BEGIN DESCRIPTION:
Dry Creek 16.0
END DESCRIPTION:
XS GIS Cut Line= 3
        1830225.       13929425.        1830375.       13929275.
      1830529.37     13928819.06
#Sta/Elev= 30
    4788 1942.46  4830.4 1939.71  4848.8 1937.37  4890.6 1931.05    4986 1917.03
  5012.2 1915.67  5012.7 1915.17  5019.5 1915.67  5021.2 1916.39  5031.8 1916.22
    5042 1918.74  5047.3 1918.28  5073.4 1921.26  5078.7 1920.48  5126.8 1921.58
  5158.5 1923.87    5173 1927.62  5197.5 1943.04  5204.4 1946.63  5211.3 1952.43
    5243 1956.23  5293.4  1960.8  5316.9 1963.87  5330.1 1966.61  5356.3 1969.44
  5380.2 1970.79  5419.1 1974.53  5443.6 1975.03  5464.4  1976.6  5481.5 1978.03
#Mann= 7 ,-1 , 0
    4788     .07       0  4848.8    .035       0  4890.6     .07       0
  5012.2     .05       0  5019.5     .07       0  5197.5      .1       0
  5464.4     .07       0
Bank Sta=5012.2,5019.5
XS Rating Curve= 0 ,0
Exp/Cntr=0.3,0.1

Type RM Length L Ch R = 1 ,7142    ,534,534,534
BEGIN DESCRIPTION:
Dry Creek 15.0
END DESCRIPTION:
XS GIS Cut Line= 3
        1830449.     13929558.29      1830780.06     13929239.27
      1831104.53     13929294.53
#Sta/Elev= 30
  4603.7 1940.72  4624.5 1938.69  4688.1 1929.13  4716.4 1927.07  4864.8 1920.01
  4907.2 1919.62  4930.1 1918.13  4956.9 1916.33  4963.8 1914.05    4971 1913.19
  5009.6 1911.24  5010.1 1910.74  5017.4 1911.24  5027.6 1911.93  5035.3 1915.71
  5055.9 1927.03  5070.7 1930.24  5088.8 1936.77  5119.2 1943.98  5130.9    1952
  5134.6 1952.48  5149.6 1953.98  5191.1 1960.76  5230.8 1968.48  5261.2 1973.23
  5306.5 1977.03  5311.9 1978.71  5342.4 1982.23  5372.8 1987.88  5392.6  1990.2
#Mann= 6 ,-1 , 0
  4603.7     .07       0  4930.1    .035       0  5009.6    .035       0
  5017.4    .035       0  5035.3     .07       0  5134.6      .1       0
Bank Sta=5009.6,5017.4
XS Rating Curve= 0 ,0
Exp/Cntr=0.3,0.1

Type RM Length L Ch R = 1 ,6608    ,485,485,485
BEGIN DESCRIPTION:
Dry Creek 14.0
END DESCRIPTION:
XS GIS Cut Line= 3
        1830625.       13929725.        1830975.       13929725.
      1831124.99       13929675.
#Sta/Elev= 30
    4650    1941  4652.5    1941    4660 1939.66    4670 1939.46    4690 1937.77
    4720 1932.93    4740 1930.63    4770 1925.55    4790 1922.66    4810  1920.5
    4870 1915.53    4900 1910.64    4920 1911.15  4941.5    1911    4970 1910.34
  4997.9 1908.27  5006.6  1908.2  5007.1  1907.7  5013.9  1907.7  5014.4  1908.2
  5031.6 1911.55  5042.2  1917.7  5052.7 1926.44  5063.2 1933.38  5084.3 1945.73
  5115.9 1960.87    5137 1966.64  5155.5 1970.51  5157.2 1970.51  5158.1 1970.51
#Mann= 6 ,-1 , 0
    4650     .07       0  4941.5    .035       0  4997.9     .07       0
  5006.6     .05       0  5014.4     .07       0  5157.2      .1       0
Bank Sta=5006.6,5014.4
XS Rating Curve= 0 ,0
Exp/Cntr=0.3,0.1

Type RM Length L Ch R = 1 ,6123    ,485,485,485
BEGIN DESCRIPTION:
Dry Creek 13.0
END DESCRIPTION:
XS GIS Cut Line= 3
      1830624.99       13930175.        1830975.       13930175.
      1831125.01     13930074.99
#Sta/Elev= 30
    4650 1946.97    4730 1937.09    4780 1928.34    4810 1922.14    4840 1917.22
    4870 1913.53    4920 1908.84    4930 1906.05    4940 1904.29  4966.1 1901.09
  4966.6 1900.59  4973.9 1901.09  5013.5 1904.65  5036.1 1904.83  5043.6  1903.8
  5064.6 1904.47  5072.1 1908.11  5079.6 1913.99  5085.6  1914.1  5094.7 1919.33
  5100.7 1919.48  5115.7 1928.49  5121.7  1929.1  5130.7 1933.81  5136.7 1934.89
  5144.2 1938.55  5166.8 1942.37  5172.8 1943.71  5177.3 1946.21  5180.3 1946.21
#Mann= 3 ,-1 , 0
    4650     .07       0  4966.1     .05       0  4973.9     .07       0
Bank Sta=4966.1,4973.9
XS Rating Curve= 0 ,0
Exp/Cntr=0.3,0.1

Type RM Length L Ch R = 1 ,5638    ,456,456,456
BEGIN DESCRIPTION:
Dry Creek 12.0
END DESCRIPTION:
XS GIS Cut Line= 3
      1830775.02       13930625.        1830875.       13930625.
      1831275.02     13930775.01
#Sta/Elev= 30
  4891.4 1930.82  4941.4 1917.57  4971.4 1905.52  4988.9 1895.48  5008.7 1894.94
  5009.2 1894.44  5016.8 1894.94  5044.8  1895.6  5055.5 1896.79  5061.7 1898.87
  5076.8 1899.12  5091.9 1901.56  5130.2 1901.94  5140.9  1904.2  5147.1 1907.18
  5152.5 1906.75    5172 1911.79  5177.4 1911.92  5209.3 1918.67  5257.5 1930.19
  5262.8 1930.24  5279.7 1935.97  5301.1 1940.29  5311.8 1944.85    5318 1949.27
  5348.3 1953.32  5365.2  1958.3  5397.2 1962.98  5403.4 1965.69  5418.6 1966.73
#Mann= 4 ,-1 , 0
  4891.4     .07       0  5008.7     .05       0  5016.8     .07       0
  5209.3      .1       0
Bank Sta=5008.7,5016.8
XS Rating Curve= 0 ,0
Exp/Cntr=0.3,0.1

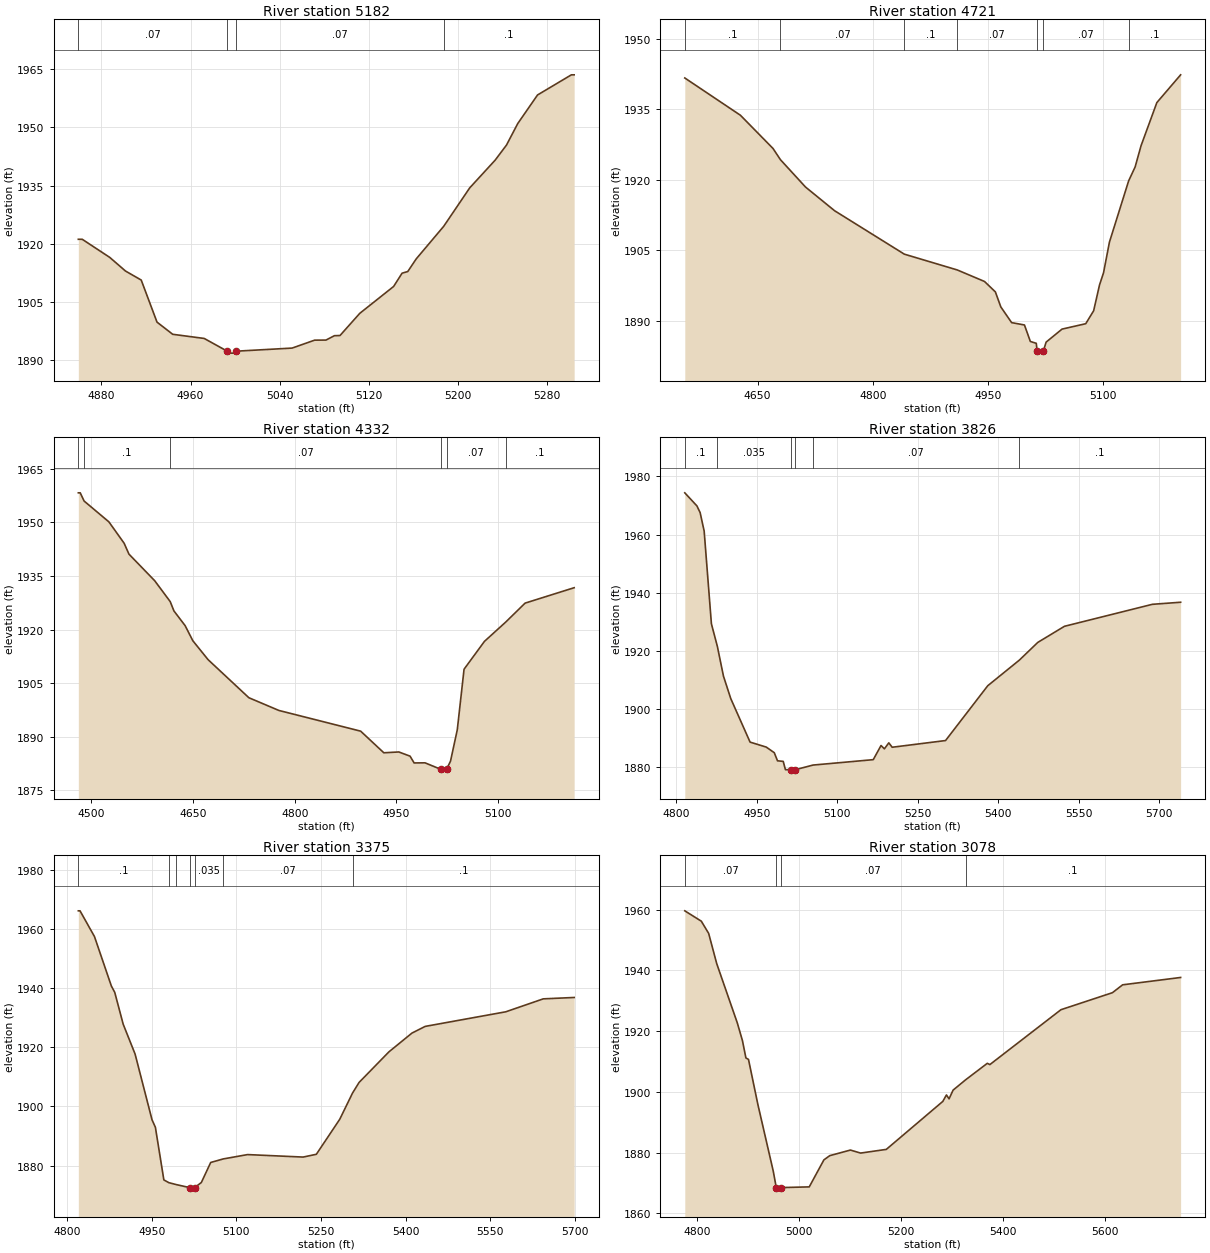
Type RM Length L Ch R = 1 ,5182    ,461,461,461
BEGIN DESCRIPTION:
Dry Creek 11.0
END DESCRIPTION:
XS GIS Cut Line= 3
      1830775.03     13930925.03        1830875.       13931025.
      1831174.99       13931075.
#Sta/Elev= 30
  4859.2 1921.17  4862.7 1921.17  4887.4 1916.51  4901.6 1912.99  4915.7 1910.67
  4929.9 1899.83    4944  1896.7  4972.3 1895.63    4993 1892.35  4993.5 1891.85
  5000.6 1891.85  5001.1 1892.35  5051.3 1893.15  5071.5 1895.19  5081.7 1895.21
  5089.3 1896.34  5094.3 1896.38  5112.1  1902.1  5142.5 1909.02  5150.1 1912.44
  5155.2 1912.86  5162.8 1916.12  5187.5 1924.51  5210.9 1934.42  5233.7 1941.54
  5243.9 1945.43    5254 1950.96  5271.8 1958.33  5302.2 1963.52  5304.7 1963.52
#Mann= 4 ,-1 , 0
  4859.2     .07       0    4993     .05       0  5001.1     .07       0
  5187.5      .1       0
Bank Sta=4993,5001.1
XS Rating Curve= 0 ,0
Exp/Cntr=0.3,0.1

Type RM Length L Ch R = 1 ,4721    ,389,389,389
BEGIN DESCRIPTION:
Dry Creek 10.0
END DESCRIPTION:
XS GIS Cut Line= 3
       1830460.5     13931116.98        1830775.       13931425.
      1830975.03     13931475.01
#Sta/Elev= 30
    4555 1941.66  4627.5 1933.73    4670 1926.66  4679.7 1924.27  4712.4 1918.45
  4750.3 1913.41  4841.2 1904.17  4910.2 1900.81  4945.7 1898.36  4959.9 1896.14
    4967 1892.94  4981.1  1889.6  4997.8  1889.1  5005.5 1885.59  5013.2  1885.2
  5014.3 1883.61  5014.8 1883.11  5022.5 1883.61  5026.1 1885.46  5046.8 1888.22
  5077.7 1889.37    5088 1892.12  5095.7 1897.64  5100.9  1900.2  5108.6 1906.73
  5133.6 1919.75  5142.1 1922.73  5149.8 1927.24  5170.4 1936.42  5201.4 1942.33
#Mann= 7 ,-1 , 0
    4555      .1       0  4679.7     .07       0  4841.2      .1       0
  4910.2     .07       0  5014.3     .05       0  5022.5     .07       0
  5133.6      .1       0
Bank Sta=5014.3,5022.5
XS Rating Curve= 0 ,0
Exp/Cntr=0.3,0.1

Type RM Length L Ch R = 1 ,4332    ,506,506,506
BEGIN DESCRIPTION:
Dry Creek 9.0
END DESCRIPTION:
XS GIS Cut Line= 3
      1830174.97     13931524.99      1830644.41     13931768.19
       1830847.3     13931758.83
#Sta/Elev= 30
  4480.6 1958.24  4483.4 1958.24  4489.1 1955.95  4525.7 1950.12  4548.2 1944.14
  4555.3  1941.1  4593.3 1933.66  4616.2 1927.82  4621.7 1925.21  4638.2  1921.1
  4649.6 1916.87  4672.1 1911.58  4732.3 1900.93  4776.6 1897.37  4897.3 1891.58
  4931.5 1885.53  4953.6 1885.76  4970.2 1884.59  4976.2 1882.69  4992.3 1882.72
  5015.7  1880.9  5016.2  1880.4    5024  1880.9  5029.9 1883.18  5039.9 1891.95
  5049.9  1908.9    5080 1916.69  5111.5 1922.11    5140 1927.39  5212.4  1931.7
#Mann= 6 ,-1 , 0
  4480.6     .07       0  4489.1      .1       0  4616.2     .07       0
  5015.7     .05       0    5024     .07       0  5111.5      .1       0
Bank Sta=5015.7,5024
XS Rating Curve= 0 ,0
Exp/Cntr=0.3,0.1

Type RM Length L Ch R = 1 ,3826    ,451,451,451
BEGIN DESCRIPTION:
Dry Creek 8.0
END DESCRIPTION:
XS GIS Cut Line= 3
      1830274.98     13932325.03        1830375.       13932175.
      1830961.95     13931717.84
#Sta/Elev= 30
    4816 1974.37  4838.6 1969.86  4844.6 1967.55  4852.1 1961.18  4865.6 1929.24
  4876.7 1921.44  4888.1 1911.18  4901.7 1903.45  4937.7 1888.45  4967.8 1886.74
  4982.8  1884.8  4988.8 1882.01  4999.5 1881.81  5003.6 1878.95  5013.8 1878.95
  5014.3 1878.45  5022.2 1878.95  5055.1 1880.54  5167.3  1882.4  5181.8 1887.27
  5188.1 1886.13  5196.3  1888.2  5202.6 1886.68  5302.1 1888.99  5380.8 1907.89
  5439.8 1916.73    5474 1922.81  5523.8 1928.37  5687.5 1935.94  5740.3 1936.66
#Mann= 6 ,-1 , 0
    4816      .1       0  4876.7    .035       0  5013.8    .035       0
  5022.2    .035       0  5055.1     .07       0  5439.8      .1       0
Bank Sta=5013.8,5022.2
XS Rating Curve= 0 ,0
Exp/Cntr=0.3,0.1

Type RM Length L Ch R = 1 ,3375    ,297,297,297
BEGIN DESCRIPTION:
Dry Creek 7.0
END DESCRIPTION:
XS GIS Cut Line= 3
      1830624.99     13932525.01        1830725.       13932375.
      1831003.51     13931733.65
#Sta/Elev= 30
  4819.6 1966.13  4822.6 1966.13  4848.2 1957.44  4878.2 1940.71  4884.2 1938.55
  4899.2 1927.78  4920.3 1917.69  4950.3 1895.48  4956.3 1892.93  4971.3 1875.14
  4980.1 1874.21  4992.7 1873.58  5017.5 1872.52    5018 1872.02  5025.9 1872.52
  5037.8 1874.26  5054.4 1881.03  5076.6 1882.23  5119.8  1883.7  5218.3 1882.86
  5241.8  1883.8  5283.3 1895.64    5306 1904.51  5317.6  1908.1  5370.6 1918.45
  5411.4 1924.79  5434.9 1927.05  5577.7 1931.98  5644.3 1936.36  5699.1 1936.83
#Mann= 7 ,-1 , 0
  4819.6      .1       0  4980.1     .07       0  4992.7    .035       0
  5017.5    .035       0  5025.9    .035       0  5076.6     .07       0
    5306      .1       0
Bank Sta=5017.5,5025.9
XS Rating Curve= 0 ,0
Exp/Cntr=0.3,0.1

Type RM Length L Ch R = 1 ,3078    ,315,315,315
BEGIN DESCRIPTION:
Dry Creek 6.0
END DESCRIPTION:
XS GIS Cut Line= 3
      1830973.89     13932647.11      1831000.96     13932444.36
      1831097.42     13931682.09
#Sta/Elev= 30
  4775.9  1959.6  4808.3 1956.19  4822.7 1952.18  4838.6 1942.19  4878.9 1922.72
    4889 1916.89  4895.8 1911.17  4900.9 1910.68  4919.3 1895.84  4949.5 1873.88
  4955.4 1868.48  4955.9 1867.98  4963.8 1868.48  5020.1 1868.72  5048.9 1877.62
  5060.4    1879  5100.8 1880.84  5120.9 1879.85  5171.3 1881.06  5282.2 1896.86
  5289.3 1898.99  5294.4  1897.7  5302.4 1900.58    5327 1903.98  5369.5  1909.4
  5374.5 1908.98    5514 1927.05    5615 1932.65    5635 1935.24  5748.8 1937.66
#Mann= 4 ,-1 , 0
  4775.9     .07       0  4955.4     .05       0  4963.8     .07       0
    5327      .1       0
Bank Sta=4955.4,4963.8
XS Rating Curve= 0 ,0
Exp/Cntr=0.3,0.1

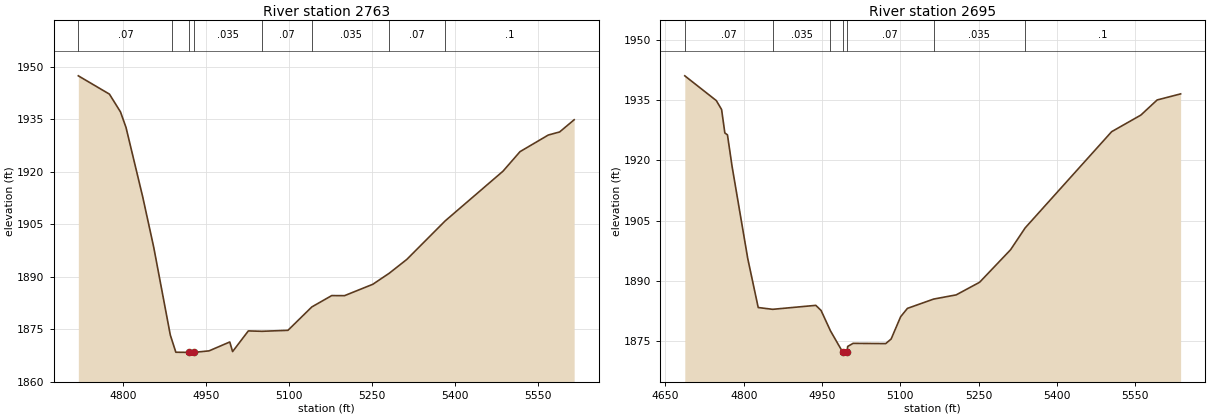
Type RM Length L Ch R = 1 ,2763    ,68,68,68
BEGIN DESCRIPTION:
Dry Creek 5.3
END DESCRIPTION:
XS GIS Cut Line= 3
      1831258.62     13932661.22      1831272.98     13932399.06
      1831135.49     13931779.28
#Sta/Elev= 30
  4718.7 1947.38    4775 1942.15    4795 1937.07    4805 1932.64  4835.1 1912.89
  4855.1 1898.47  4885.2 1873.33  4888.9 1871.52  4895.2 1868.43  4919.3 1868.39
  4919.8 1867.89  4927.7 1868.39  4955.3 1868.82  4992.8 1871.36  4997.9 1868.62
  5026.4 1874.52  5051.1 1874.41  5098.1 1874.69  5141.3 1881.37  5177.3 1884.61
  5200.5 1884.59  5251.7 1887.84  5281.3 1890.98  5313.2 1894.94  5382.7 1905.95
  5487.3 1920.14  5518.1 1925.72  5569.3 1930.47  5589.8 1931.35  5616.1 1934.83
#Mann= 8 ,-1 , 0
  4718.7     .07       0  4888.9    .035       0  4919.3    .035       0
  4927.7    .035       0  5051.1     .07       0  5141.3    .035       0
  5281.3     .07       0  5382.7      .1       0
Bank Sta=4919.3,4927.7
XS Rating Curve= 0 ,0
Exp/Cntr=0.3,0.1

Type RM Length L Ch R = 1 ,2695    ,112,112,112
BEGIN DESCRIPTION:
Dry Creek 6.5
END DESCRIPTION:
XS GIS Cut Line= 3
      1831345.61     13932645.27      1831324.78     13932357.09
      1831144.23     13931721.68
#Sta/Elev= 30
  4687.2 1941.14  4747.6 1934.95  4757.7 1932.71  4763.9 1926.87  4768.9  1926.4
  4777.7 1918.56  4807.8 1895.48  4827.8 1883.28  4855.4 1882.83  4938.1 1883.82
  4948.2 1882.54  4966.2 1877.44  4989.6 1872.14  4990.1 1871.64    4998 1872.14
  4999.1 1873.56  5009.5 1874.33  5071.9 1874.27  5082.3 1875.41  5100.6 1880.99
  5113.5 1883.06  5163.5 1885.38    5207 1886.44  5251.8 1889.59    5311  1897.7
  5339.1 1903.18  5504.6 1927.19  5560.5 1931.33  5591.7 1935.11  5636.7 1936.63
#Mann= 7 ,-1 , 0
  4687.2     .07       0  4855.4    .035       0  4966.2     .07       0
  4989.6     .05       0    4998     .07       0  5163.5    .035       0
  5339.1      .1       0
Bank Sta=4989.6,4998
XS Rating Curve= 0 ,0
Exp/Cntr=0.3,0.1