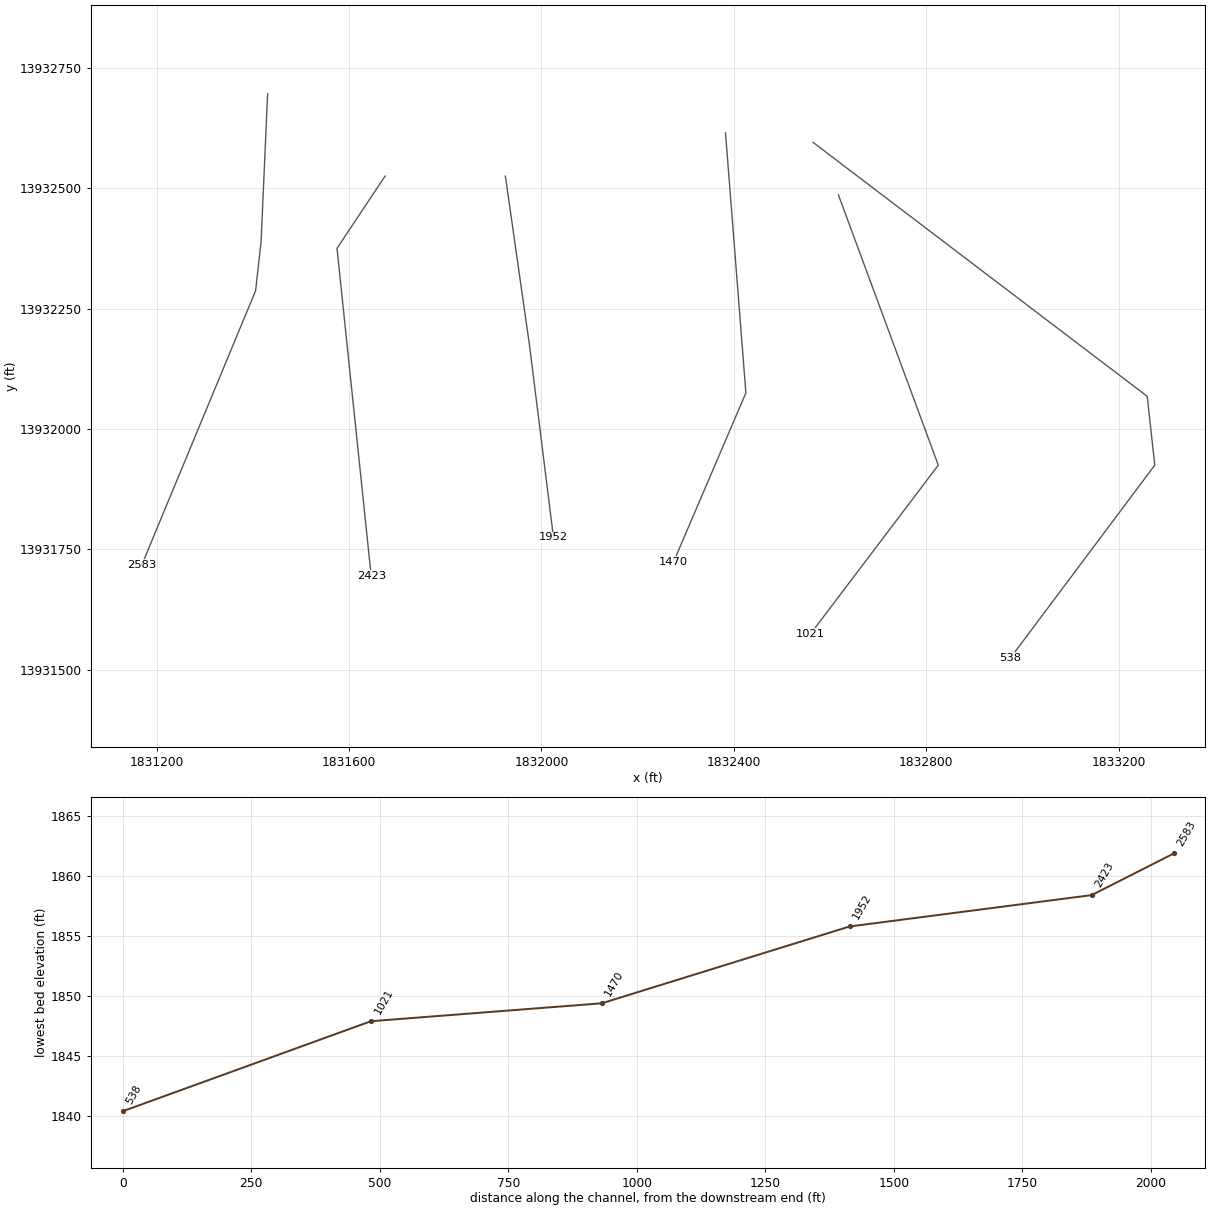
HEC-RAS study Dry Creek.prj: Dry Creek Base Level Engineering

--- Dry Creek.g01 (geometry) --- (continued)

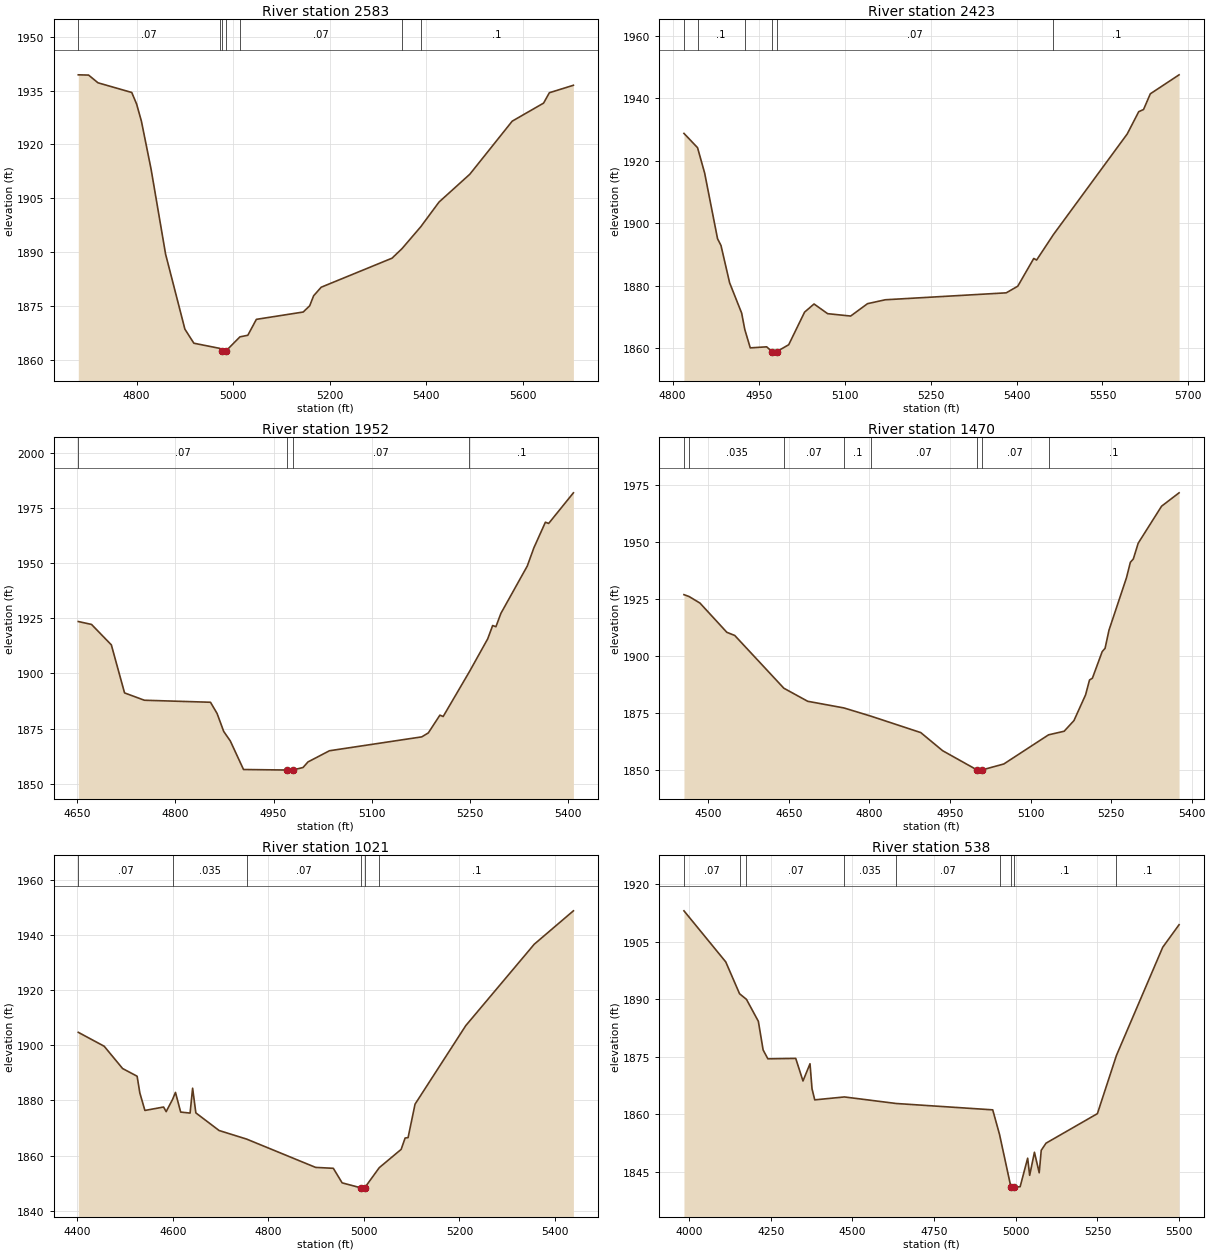
Type RM Length L Ch R = 1 ,2583    ,160,160,160
BEGIN DESCRIPTION:
Dry Creek 5.1
END DESCRIPTION:
XS GIS Cut Line= 4
      1831430.75     13932695.71      1831417.17     13932388.97
      1831405.77     13932287.04      1831169.22     13931717.95
#Sta/Elev= 30
  4679.3 1939.38  4700.6 1939.31  4720.1 1937.16  4790.1 1934.46  4800.1 1931.25
  4810.1 1926.46  4830.2 1913.04  4860.2 1889.42  4900.2 1868.52  4918.8 1864.61
  4972.9 1863.16  4976.1 1862.35  4976.6 1861.85  4984.5 1862.35  5014.2 1866.38
  5030.6 1866.83  5048.3 1871.26  5145.3  1873.3  5158.8 1875.04  5166.9 1877.82
  5182.6 1880.21  5329.4  1888.3    5350 1890.95    5389 1897.07  5426.8 1903.94
  5490.6 1911.69  5578.4 1926.47  5643.4  1931.5  5655.4 1934.39  5705.2 1936.47
#Mann= 7 ,-1 , 0
  4679.3     .07       0  4972.9    .035       0  4976.1    .035       0
  4984.5    .035       0  5014.2     .07       0    5350    .035       0
    5389      .1       0
Bank Sta=4976.1,4984.5
XS Rating Curve= 0 ,0
Exp/Cntr=0.3,0.1

Type RM Length L Ch R = 1 ,2423    ,471,471,471
BEGIN DESCRIPTION:
Dry Creek 5.0
END DESCRIPTION:
XS GIS Cut Line= 3
      1831675.03     13932525.04        1831575.       13932375.
      1831646.09     13931695.03
#Sta/Elev= 30
  4819.7 1928.72  4843.4 1924.15  4855.8 1916.02  4878.3    1895  4884.3 1892.85
  4899.4 1880.88  4920.4 1871.18  4925.8 1865.97  4935.4 1860.06    4964  1860.4
  4973.2 1858.88  4973.7 1858.38  4981.7 1858.88  5002.5 1861.07  5030.2 1871.51
  5046.7 1874.11  5070.4 1871.01  5110.6 1870.25    5140 1874.21    5171 1875.46
  5382.1 1877.68  5402.2  1879.8  5430.1 1888.68  5435.1 1888.18  5464.5 1896.35
  5593.2 1928.54  5613.3 1935.67  5621.7 1936.37  5633.5 1941.39  5683.7 1947.47
#Mann= 6 ,-1 , 0
  4819.7     .07       0  4843.4      .1       0  4925.8     .07       0
  4973.2     .05       0  4981.7     .07       0  5464.5      .1       0
Bank Sta=4973.2,4981.7
XS Rating Curve= 0 ,0
Exp/Cntr=0.3,0.1

Type RM Length L Ch R = 1 ,1952    ,482,482,482
BEGIN DESCRIPTION:
Dry Creek 4.0
END DESCRIPTION:
XS GIS Cut Line= 3
        1831925.     13932524.97        1831975.       13932175.
        1832025.     13931775.04
#Sta/Elev= 30
  4651.6 1923.54  4671.8 1922.23  4702.1 1912.97  4722.3  1891.2  4752.6 1887.88
  4853.6 1886.97  4863.7 1881.88  4873.8 1873.76  4883.9 1869.44  4904.1  1856.5
  4970.5 1856.27    4971 1855.77  4979.2 1856.27    4995 1857.41  5002.6 1859.93
  5035.4    1865  5176.5 1871.29  5186.5 1873.08  5204.2 1881.13  5209.2 1880.52
  5249.4 1900.88  5277.2 1915.66  5284.8 1921.73  5289.8 1921.19  5297.4 1927.23
  5337.7 1948.67  5347.8 1956.93  5365.4 1968.52  5370.4 1967.98  5408.2 1981.84
#Mann= 4 ,-1 , 0
  4651.6     .07       0  4970.5     .05       0  4979.2     .07       0
  5249.4      .1       0
Bank Sta=4970.5,4979.2
XS Rating Curve= 0 ,0
Exp/Cntr=0.3,0.1

Type RM Length L Ch R = 1 ,1470    ,449,449,449
BEGIN DESCRIPTION:
Dry Creek 3.0
END DESCRIPTION:
XS GIS Cut Line= 3
      1832382.62     13932614.66        1832425.       13932075.
      1832275.01     13931725.01
#Sta/Elev= 30
  4454.5 1926.94  4464.2 1926.09  4484.3 1923.24  4534.4 1910.38  4549.1    1909
  4640.5 1885.82  4684.9 1880.08  4752.4 1877.15  4803.2  1873.5  4895.5 1866.32
  4936.3 1858.35  5000.5 1849.88    5001 1849.38  5009.2 1849.88  5050.2 1852.52
  5133.5 1865.33  5162.6 1866.91  5180.8 1871.58  5202.5 1882.92  5209.8 1889.42
  5215.2 1890.23  5233.4 1901.89  5238.8 1903.36  5246.1 1911.36  5278.7 1934.41
  5285.9 1941.17  5291.4 1942.62  5300.5 1949.56    5344 1965.81  5376.6 1971.69
#Mann= 8 ,-1 , 0
  4454.5     .07       0  4464.2    .035       0  4640.5     .07       0
  4752.4      .1       0  4803.2     .07       0  5000.5     .05       0
  5009.2     .07       0  5133.5      .1       0
Bank Sta=5000.5,5009.2
XS Rating Curve= 0 ,0
Exp/Cntr=0.3,0.1

Type RM Length L Ch R = 1 ,1021    ,483,483,483
BEGIN DESCRIPTION:
Dry Creek 2.0
END DESCRIPTION:
XS GIS Cut Line= 3
      1832617.36     13932485.87        1832825.       13931925.
      1832559.84     13931575.46
#Sta/Elev= 30
  4401.8 1904.69    4456 1899.65  4494.6 1891.57    4525 1888.79  4530.7 1882.72
  4541.3 1876.39  4580.4 1877.63  4585.8 1875.96  4599.3 1880.42  4605.3 1882.93
  4616.2  1875.8  4635.9 1875.43  4641.2 1884.45    4648  1875.5  4696.7 1869.12
  4754.2 1866.02  4898.8 1855.76  4935.9 1855.43  4954.3 1850.16  4992.9 1848.39
  4993.4 1847.89  5001.6 1848.39  5032.1 1855.67  5077.9 1862.29  5086.2  1866.4
  5092.4 1866.55    5107 1878.67  5213.2 1907.11  5356.6  1936.6  5438.6  1948.7
#Mann= 6 ,-1 , 0
  4401.8     .07       0  4599.3    .035       0  4754.2     .07       0
  4992.9     .05       0  5001.6     .07       0  5032.1      .1       0
Bank Sta=4992.9,5001.6
XS Rating Curve= 0 ,0
Exp/Cntr=0.3,0.1

Type RM Length L Ch R = 1 ,538     ,0,0,0
BEGIN DESCRIPTION:
Dry Creek 1.0
END DESCRIPTION:
XS GIS Cut Line= 4
      1832564.82     13932594.79      1833259.35     13932067.82
        1833275.       13931925.        1832975.       13931525.
#Sta/Elev= 30
  3984.5  1913.1  4112.4 1899.76  4154.7 1891.44  4175.8 1889.97  4212.2 1884.24
  4226.8 1876.76  4241.3 1874.44  4326.6 1874.55  4348.8 1868.65  4370.3 1873.15
  4376.5 1866.61  4384.8 1863.72  4475.6 1864.48  4634.1 1862.77  4929.6 1861.11
  4950.5 1854.66  4985.4  1840.9  4985.9  1840.4  4994.4  1840.9  5013.5 1841.03
  5036.5 1848.48  5042.7    1844  5057.3 1850.03  5071.9 1844.67  5078.1 1850.54
  5092.7  1852.4    5250 1860.12  5308.3 1875.33    5450 1903.59    5500 1909.47
#Mann= 9 ,-1 , 0
  3984.5     .07       0  4154.7      .1       0  4175.8     .07       0
  4475.6    .035       0  4634.1     .07       0  4950.5      .1       0
  4985.4     .05       0  4994.4      .1       0  5308.3      .1       0
Bank Sta=4985.4,4994.4
XS Rating Curve= 0 ,0
Exp/Cntr=0.3,0.1

Chan Stop Cuts=-1
Use User Specified Reach Order=0
Composite Channel Slope=5