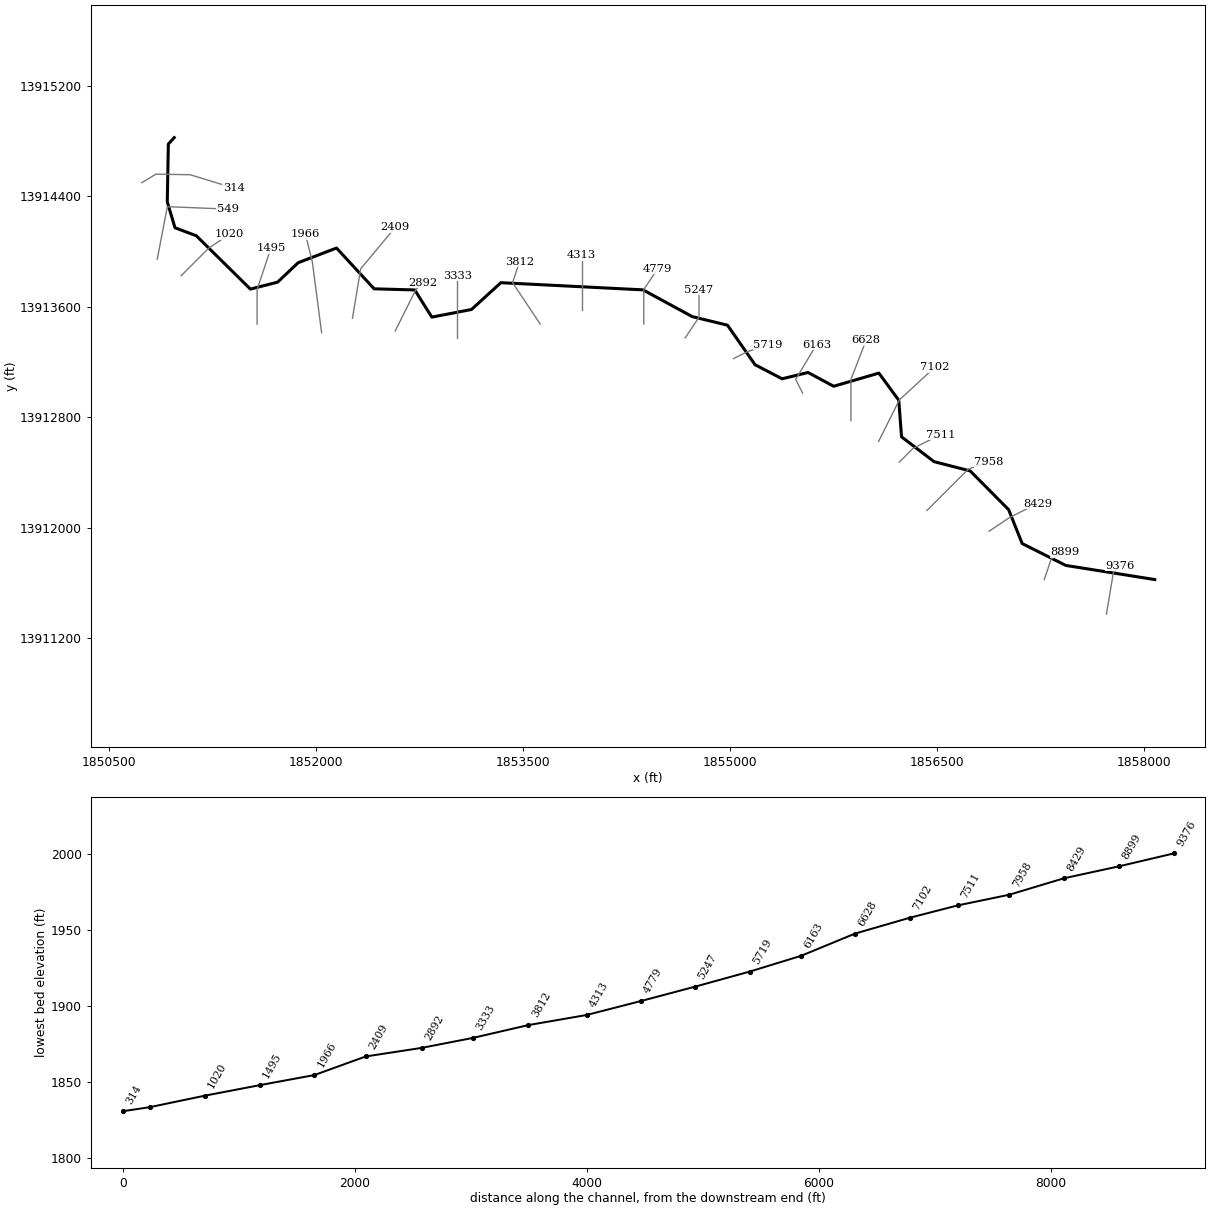
--- Edmunson Creek.prj (project) ---

Proj Title=Edmunson Creek Base Level Engineering
Current Plan=p01
Default Exp/Contr=0.3,0.1
English Units
Geom File=g01
Flow File=f01
Plan File=p01
BEGIN DESCRIPTION:
Edmunson Creek
END DESCRIPTION:

--- Edmunson Creek.p01 (plan) ---

Plan Title=Multiple Run
Short Identifier=Multiple
Geom File=g01
Flow File=f01
Subcritical Flow
K Sum by GR= 0
Std Step Tol= 0.01
Critical Tol= 0.01
Num of Std Step Trials= 20
Max Error Tol= 0.3
Flow Tol Ratio= 0.001
Split Flow NTrial= 30
Split Flow Tol= 0.02
Split Flow Ratio= 0.02
Log Output Level= 0
Friction Slope Method= 1
Unsteady Friction Slope Method= 2
Unsteady Bridges Friction Slope Method= 1
Parabolic Critical Depth
Global Vel Dist=  1 , 1 , 1
Global Log Level= 0
CheckData=True
Encroach Param= -1, 0, 0, 0
BEGIN DESCRIPTION:
Multiple Run
END DESCRIPTION:

--- Edmunson Creek.f01 (steady flow) ---

Flow Title=Multiple
Number of Profiles=7
Profile Names=10-year,25-year,50-year,1pct_min,100-year,1pct_plu,500-year
River Rch & RM= Edmunson Creek,Reach-1,9376
     739    1238    1705    1139    2272    4533    3979
River Rch & RM= Edmunson Creek,Reach-1,7102
    1206    2083    2928    1990    3970    7920    7209
Boundary for River Rch & Prof#=Edmunson Creek,Reach-1,1
Up Type=0
Dn Type=3
Dn Slope=0.005
Boundary for River Rch & Prof#=Edmunson Creek,Reach-1,2
Up Type=0
Dn Type=3
Dn Slope=0.005
Boundary for River Rch & Prof#=Edmunson Creek,Reach-1,3
Up Type=0
Dn Type=3
Dn Slope=0.005
Boundary for River Rch & Prof#=Edmunson Creek,Reach-1,4
Up Type=0
Dn Type=3
Dn Slope=0.005
Boundary for River Rch & Prof#=Edmunson Creek,Reach-1,5
Up Type=0
Dn Type=3
Dn Slope=0.005
Boundary for River Rch & Prof#=Edmunson Creek,Reach-1,6
Up Type=0
Dn Type=3
Dn Slope=0.005
Boundary for River Rch & Prof#=Edmunson Creek,Reach-1,7
Up Type=0
Dn Type=3
Dn Slope=0.005

--- Edmunson Creek.g01 (geometry) ---

Geom Title=Existing Conditions

River Reach=Edmunson Creek,Reach-1
Reach XY= 30
      1858075.00     13911625.00      1857430.93     13911727.25
      1857114.94     13911885.61      1857016.86     13912131.06
      1856738.30     13912411.60      1856476.58     13912478.82
      1856241.39     13912658.33      1856221.24     13912923.44
      1856077.31     13913119.92      1855750.00     13913024.59
      1855564.38     13913124.39      1855376.58     13913078.67
      1855180.58     13913180.58      1854981.06     13913466.86
      1854726.56     13913528.76      1854369.06     13913722.74
      1853340.16     13913774.62      1853127.43     13913580.52
      1852840.04     13913525.31      1852716.72     13913721.94
      1852422.30     13913730.36      1852150.04     13914025.51
      1851872.57     13913919.48      1851723.50     13913778.61
      1851526.63     13913728.13      1851134.78     13914114.48
      1850980.40     13914172.29      1850924.57     13914359.82
      1850932.27     13914778.44      1850975.00     13914825.00

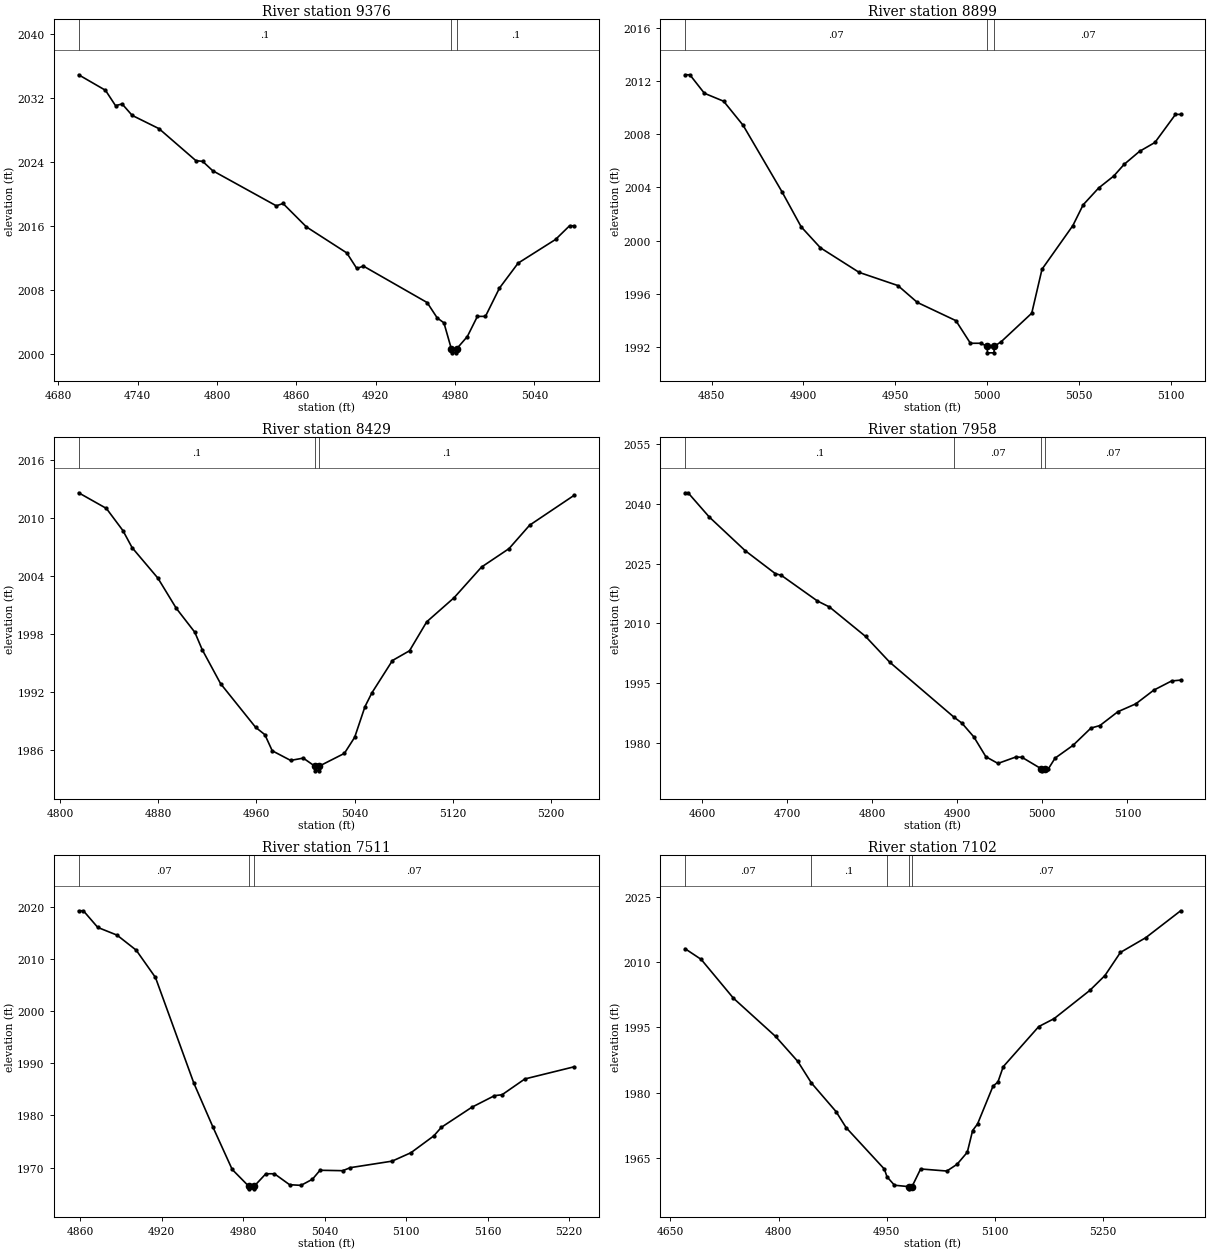
Type RM Length L Ch R = 1,9376,477,477,477
BEGIN DESCRIPTION:
Edmunson Creek 20.0
END DESCRIPTION:
XS GIS Cut Line= 3
      1857725.00     13911375.00      1857775.00     13911675.00
      1857824.97     13911724.97
#Sta/Elev= 30
  4695.3 2034.89  4715.6 2032.95  4723.2 2031.03  4728.2 2031.24  4735.8 2029.81
  4756.1 2028.15  4784.0 2024.15  4789.1 2024.06  4796.7 2022.89  4844.8 2018.50
  4849.9 2018.79  4867.6 2015.86  4898.1 2012.61  4905.7 2010.66  4910.7 2010.96
  4958.9 2006.40  4966.5 2004.48  4971.6 2003.86  4977.2 2000.61  4977.4 2000.11
  4980.9 2000.11  4981.2 2000.61  4989.3 2002.15  4996.9 2004.67  5003.0 2004.67
  5013.6 2008.21  5027.7 2011.33  5056.0 2014.29  5066.6 2016.00  5070.1 2016.00
#Mann=3,-1,0
  4695.3     0.1       0  4977.2    0.05       0  4981.2     0.1       0
Bank Sta=4977.2,4981.2
Exp/Cntr=0.3,0.1

Type RM Length L Ch R = 1,8899,470,470,470
BEGIN DESCRIPTION:
Edmunson Creek 19.0
END DESCRIPTION:
XS GIS Cut Line= 3
      1857275.01     13911625.04      1857325.00     13911775.00
      1857425.02     13911825.01
#Sta/Elev= 30
  4835.6 2012.47  4838.2 2012.47  4846.1 2011.08  4856.6 2010.48  4867.2 2008.67
  4888.3 2003.69  4898.8 2001.04  4909.3 1999.46  4930.4 1997.61  4951.5 1996.62
  4962.1 1995.35  4983.1 1993.98  4991.0 1992.28  4996.5 1992.28  5000.1 1992.06
  5000.3 1991.56  5003.8 1991.56  5004.1 1992.06  5007.7 1992.39  5024.4 1994.54
  5030.0 1997.85  5046.8 2001.13  5052.4 2002.69  5060.8 2003.95  5069.1 2004.86
  5074.7 2005.73  5083.1 2006.71  5091.5 2007.38  5102.7 2009.49  5105.5 2009.49
#Mann=3,-1,0
  4835.6    0.07       0  5000.1    0.05       0  5004.1    0.07       0
Bank Sta=5000.1,5004.1
Exp/Cntr=0.3,0.1

Type RM Length L Ch R = 1,8429,471,471,471
BEGIN DESCRIPTION:
Edmunson Creek 18.0
END DESCRIPTION:
XS GIS Cut Line= 3
      1856874.98     13911974.99      1857025.00     13912075.00
      1857224.99     13912175.00
#Sta/Elev= 30
  4815.1 2012.62  4837.7 2011.00  4851.2 2008.70  4858.7 2006.93  4879.7 2003.77
  4894.7 2000.64  4909.8 1998.16  4915.8 1996.36  4930.8 1992.83  4959.3 1988.31
  4966.9 1987.54  4972.9 1985.87  4987.9 1984.87  4998.2 1985.11  5007.4 1984.29
  5007.6 1983.79  5011.1 1983.79  5011.4 1984.29  5031.7 1985.60  5040.1 1987.27
  5048.5 1990.45  5054.1 1991.87  5070.9 1995.23  5084.8 1996.24  5098.8 1999.24
  5121.2 2001.75  5143.5 2004.92  5165.9 2006.83  5182.7 2009.26  5219.0 2012.36
#Mann=3,-1,0
  4815.1     0.1       0  5007.4    0.05       0  5011.4     0.1       0
Bank Sta=5007.4,5011.4
Exp/Cntr=0.3,0.1

Type RM Length L Ch R = 1,7958,447,447,447
BEGIN DESCRIPTION:
Edmunson Creek 17.0
END DESCRIPTION:
XS GIS Cut Line= 3
      1856425.00     13912125.00      1856725.00     13912425.00
      1856875.02     13912475.01
#Sta/Elev= 30
  4580.1 2042.81  4583.6 2042.81  4608.4 2036.75  4650.8 2028.26  4686.2 2022.50
  4693.2 2022.08  4735.7 2015.63  4749.8 2014.13  4792.2 2006.74  4820.5 2000.29
  4895.6 1986.56  4905.4 1984.98  4919.5 1981.50  4933.6 1976.53  4947.8 1974.85
  4969.0 1976.48  4976.1 1976.38  4998.8 1973.49  4999.1 1972.99  5002.8 1973.49
  5007.0 1973.49  5014.9 1976.17  5036.0 1979.39  5057.1 1983.73  5067.6 1984.36
  5088.7 1987.83  5109.8 1989.81  5130.9 1993.25  5151.9 1995.56  5162.5 1995.77
#Mann=4,-1,0
  4580.1     0.1       0  4895.6    0.07       0  4998.8    0.05       0
  5002.8    0.07       0
Bank Sta=4998.8,5002.8
Exp/Cntr=0.3,0.1

Type RM Length L Ch R = 1,7511,409,409,409
BEGIN DESCRIPTION:
Edmunson Creek 16.0
END DESCRIPTION:
XS GIS Cut Line= 3
      1856225.00     13912475.00      1856325.00     13912575.00
      1856524.97     13912674.98
#Sta/Elev= 30
  4858.8 2019.24  4862.3 2019.24  4872.9 2016.05  4887.1 2014.57  4901.2 2011.69
  4915.4 2006.45  4943.7 1986.17  4957.8 1977.73  4971.9 1969.65  4984.1 1966.43
  4984.3 1965.93  4987.8 1965.93  4988.1 1966.43  4996.7 1968.82  5003.0 1968.82
  5014.2 1966.72  5022.6 1966.60  5031.0 1967.77  5036.6 1969.49  5053.3 1969.41
  5058.9 1969.99  5089.7 1971.24  5103.6 1972.86  5120.4 1976.08  5126.0 1977.73
  5148.4 1981.57  5165.1 1983.79  5170.7 1983.97  5187.5 1987.00  5223.8 1989.33
#Mann=3,-1,0
  4858.8    0.07       0  4984.1    0.05       0  4988.1    0.07       0
Bank Sta=4984.1,4988.1
Exp/Cntr=0.3,0.1

Type RM Length L Ch R = 1,7102,474,474,474
BEGIN DESCRIPTION:
Edmunson Creek 15.0
END DESCRIPTION:
XS GIS Cut Line= 3
      1856075.01     13912625.03      1856225.00     13912925.00
      1856484.16     13913164.12
#Sta/Elev= 30
  4670.3 2013.09  4692.6 2010.64  4737.4 2001.72  4796.0 1992.92  4826.8 1987.19
  4845.7 1982.23  4879.9 1975.66  4893.9 1971.97  4947.0 1962.44  4950.6 1960.68
  4961.0 1958.74  4981.3 1958.41  4981.6 1957.91  4985.3 1958.41  4997.3 1962.48
  5033.7 1962.00  5047.9 1963.55  5062.1 1966.32  5069.5 1971.31  5076.3 1972.81
  5097.8 1981.51  5104.6 1982.45  5112.0 1985.98  5161.3 1995.20  5182.6 1997.02
  5232.2 2003.51  5253.2 2006.93  5274.7 2012.24  5309.9 2015.63  5358.3 2021.81
#Mann=5,-1,0
  4670.3    0.07       0  4845.7     0.1       0  4950.6    0.07       0
  4981.3    0.05       0  4985.3    0.07       0
Bank Sta=4981.3,4985.3
Exp/Cntr=0.3,0.1

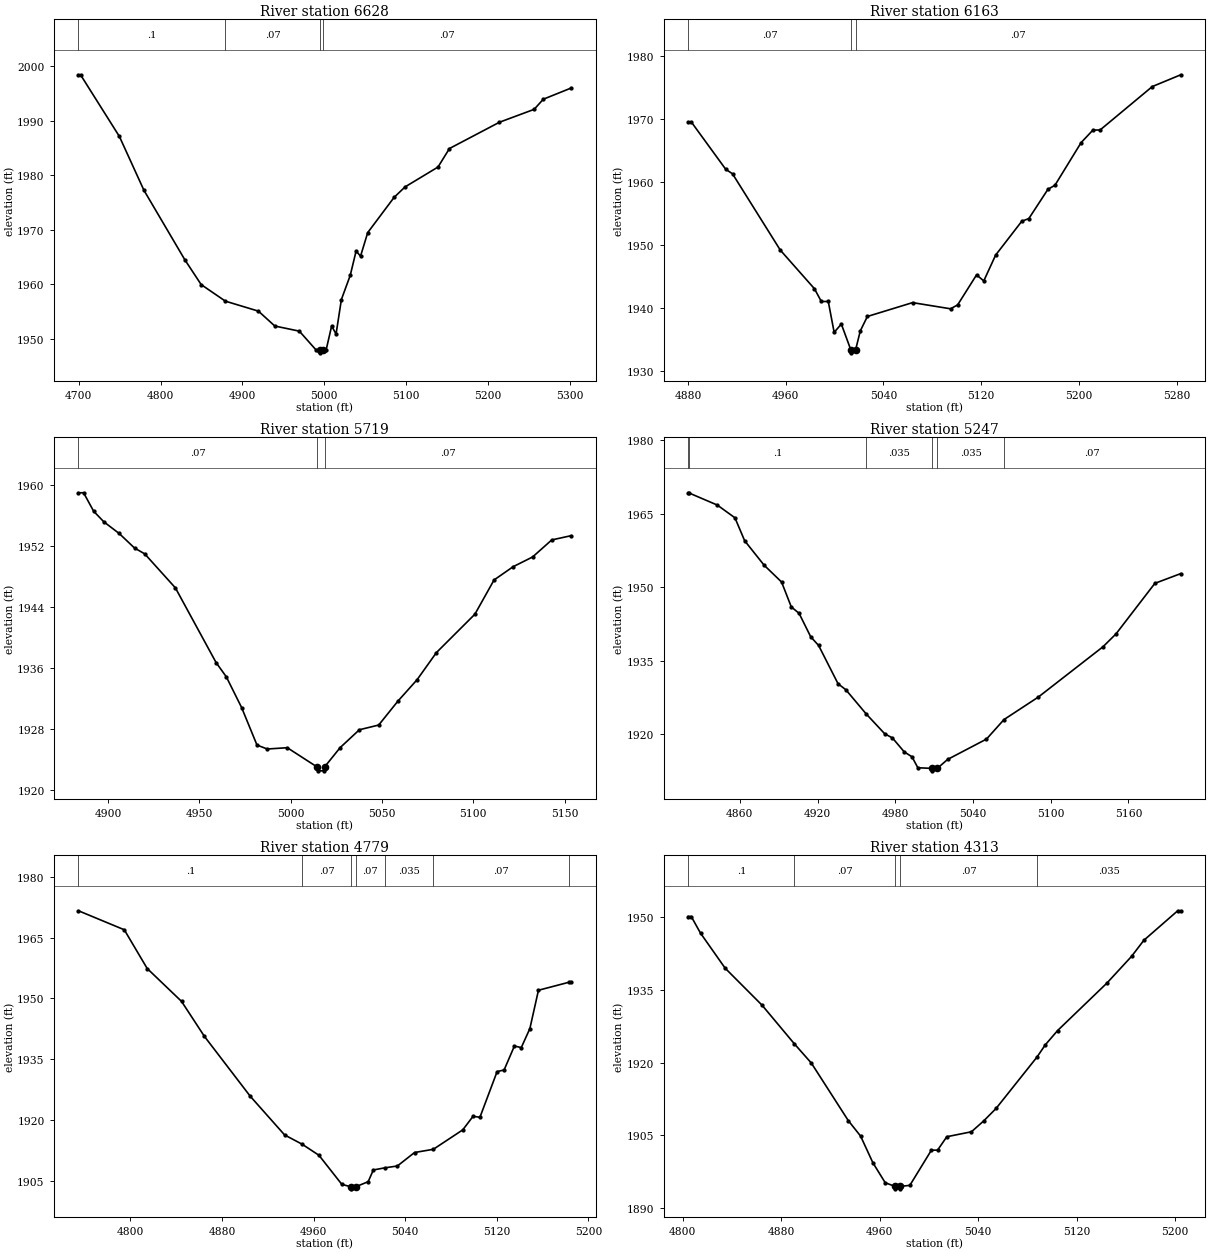
Type RM Length L Ch R = 1,6628,465,465,465
BEGIN DESCRIPTION:
Edmunson Creek 14.0
END DESCRIPTION:
XS GIS Cut Line= 3
      1855875.00     13912775.03      1855875.00     13913075.00
      1855984.68     13913356.63
#Sta/Elev= 30
  4699.7 1998.37  4702.2 1998.37  4749.7 1987.08  4779.7 1977.23  4829.7 1964.51
  4849.7 1959.96  4879.3 1956.93  4919.7 1955.10  4939.7 1952.38  4969.7 1951.44
  4989.7 1948.07  4995.2 1947.97  4995.4 1947.47  4999.2 1947.97  5002.4 1947.97
  5009.2 1952.39  5014.6 1950.91  5021.1 1957.23  5031.9 1961.64  5039.1 1966.11
  5044.5 1965.16  5053.3 1969.48  5085.5 1975.92  5098.9 1977.84  5139.2 1981.48
  5153.2 1984.87  5214.3 1989.68  5256.7 1992.04  5268.0 1993.90  5301.9 1995.94
#Mann=4,-1,0
  4699.7     0.1       0  4879.3    0.07       0  4995.2    0.05       0
  4999.2    0.07       0
Bank Sta=4995.2,4999.2
Exp/Cntr=0.3,0.1

Type RM Length L Ch R = 1,6163,444,444,444
BEGIN DESCRIPTION:
Edmunson Creek 13.0
END DESCRIPTION:
XS GIS Cut Line= 3
      1855524.98     13912975.04      1855475.00     13913075.00
      1855625.00     13913325.00
#Sta/Elev= 30
  4880.2 1969.52  4882.9 1969.52  4910.9 1962.05  4916.5 1961.32  4955.6 1949.20
  4983.6 1943.05  4989.2 1941.03  4994.9 1941.03  4999.7 1936.13  5005.6 1937.44
  5013.3 1933.37  5013.5 1932.87  5017.3 1933.37  5021.1 1936.35  5026.9 1938.65
  5063.9 1940.85  5095.0 1939.87  5100.8 1940.49  5116.3 1945.26  5122.2 1944.30
  5131.9 1948.40  5153.3 1953.78  5159.1 1954.21  5174.7 1958.85  5180.5 1959.51
  5201.9 1966.28  5211.6 1968.28  5217.4 1968.28  5260.2 1975.19  5283.5 1977.06
#Mann=3,-1,0
  4880.2    0.07       0  5013.3    0.05       0  5017.3    0.07       0
Bank Sta=5013.3,5017.3
Exp/Cntr=0.3,0.1

Type RM Length L Ch R = 1,5719,472,472,472
BEGIN DESCRIPTION:
Edmunson Creek 12.0
END DESCRIPTION:
XS GIS Cut Line= 3
      1855025.04     13913225.02      1855125.00     13913275.00
      1855275.03     13913325.01
#Sta/Elev= 30
  4883.7 1959.04  4886.5 1959.04  4892.0 1956.62  4897.6 1955.22  4906.0 1953.69
  4914.4 1951.78  4920.0 1951.01  4936.8 1946.54  4959.1 1936.72  4964.7 1934.85
  4973.1 1930.80  4981.5 1925.88  4987.1 1925.36  4998.1 1925.53  5014.5 1922.99
  5014.8 1922.49  5018.3 1922.49  5018.5 1922.99  5027.1 1925.55  5037.6 1927.89
  5048.2 1928.51  5058.7 1931.65  5069.2 1934.46  5079.8 1938.03  5100.9 1943.08
  5111.4 1947.58  5121.9 1949.33  5132.5 1950.60  5143.0 1952.84  5153.6 1953.40
#Mann=3,-1,0
  4883.7    0.07       0  5014.5    0.05       0  5018.5    0.07       0
Bank Sta=5014.5,5018.5
Exp/Cntr=0.3,0.1

Type RM Length L Ch R = 1,5247,468,468,468
BEGIN DESCRIPTION:
Edmunson Creek 11.0
END DESCRIPTION:
XS GIS Cut Line= 3
      1854675.00     13913375.00      1854775.00     13913525.00
      1854775.00     13913725.02
#Sta/Elev= 30
  4820.1 1969.31  4820.4 1969.31  4842.6 1966.80  4856.2 1964.20  4863.7 1959.52
  4878.7 1954.54  4892.2 1951.10  4899.7 1946.02  4905.7 1944.72  4914.7 1939.92
  4920.8 1938.15  4935.8 1930.34  4941.8 1929.12  4957.5 1924.19  4971.8 1920.14
  4977.8 1919.28  4986.9 1916.44  4992.9 1915.43  4997.4 1913.20  5008.4 1913.07
  5008.6 1912.57  5012.4 1913.07  5020.4 1914.90  5050.4 1919.05  5063.9 1923.03
  5090.4 1927.62  5140.4 1937.90  5150.4 1940.52  5180.4 1950.83  5200.4 1952.82
#Mann=6,-1,0
  4820.1    0.07       0  4820.4     0.1       0  4957.5   0.035       0
  5008.4   0.035       0  5012.4   0.035       0  5063.9    0.07       0
Bank Sta=5008.4,5012.4
Exp/Cntr=0.3,0.1

Type RM Length L Ch R = 1,4779,466,466,466
BEGIN DESCRIPTION:
Edmunson Creek 10.0
END DESCRIPTION:
XS GIS Cut Line= 3
      1854375.00     13913475.03      1854375.00     13913725.00
      1854474.98     13913874.96
#Sta/Elev= 30
  4754.6 1971.60  4794.6 1966.92  4814.6 1957.38  4844.6 1949.28  4864.6 1940.65
  4904.6 1925.91  4934.6 1916.38  4950.0 1914.08  4964.6 1911.37  4984.6 1904.20
  4992.6 1903.60  4992.8 1903.10  4996.6 1903.60  5007.6 1904.86  5012.1 1907.75
  5022.1 1908.27  5033.1 1908.73  5048.1 1912.05  5064.5 1912.84  5090.2 1917.63
  5099.2 1920.97  5105.2 1920.73  5120.2 1931.99  5126.3 1932.38  5135.3 1938.28
  5141.3 1937.90  5148.8 1942.57  5156.3 1952.02  5183.3 1954.02  5184.8 1954.02
#Mann=7,-1,0
  4754.6     0.1       0  4950.0    0.07       0  4992.6    0.05       0
  4996.6    0.07       0  5022.1   0.035       0  5064.5    0.07       0
  5183.3   0.035       0
Bank Sta=4992.6,4996.6
Exp/Cntr=0.3,0.1

Type RM Length L Ch R = 1,4313,501,501,501
BEGIN DESCRIPTION:
Edmunson Creek 9.0
END DESCRIPTION:
XS GIS Cut Line= 3
      1853925.00     13913575.03      1853925.00     13913775.00
      1853925.00     13913975.03
#Sta/Elev= 30
  4804.6 1950.15  4807.1 1950.15  4814.6 1946.73  4834.6 1939.50  4864.6 1931.86
  4890.9 1923.87  4904.6 1919.93  4934.6 1908.06  4944.6 1904.86  4954.6 1899.35
  4964.6 1895.24  4972.6 1894.48  4972.8 1893.98  4976.3 1893.98  4976.6 1894.48
  4984.6 1894.70  5002.1 1901.96  5007.1 1901.96  5014.6 1904.73  5034.6 1905.75
  5044.6 1908.00  5054.6 1910.56  5087.8 1921.15  5094.6 1923.69  5104.6 1926.64
  5144.6 1936.42  5164.6 1941.93  5174.6 1945.25  5202.1 1951.34  5204.6 1951.34
#Mann=5,-1,0
  4804.6     0.1       0  4890.9    0.07       0  4972.6    0.05       0
  4976.6    0.07       0  5087.8   0.035       0
Bank Sta=4972.6,4976.6
Exp/Cntr=0.3,0.1

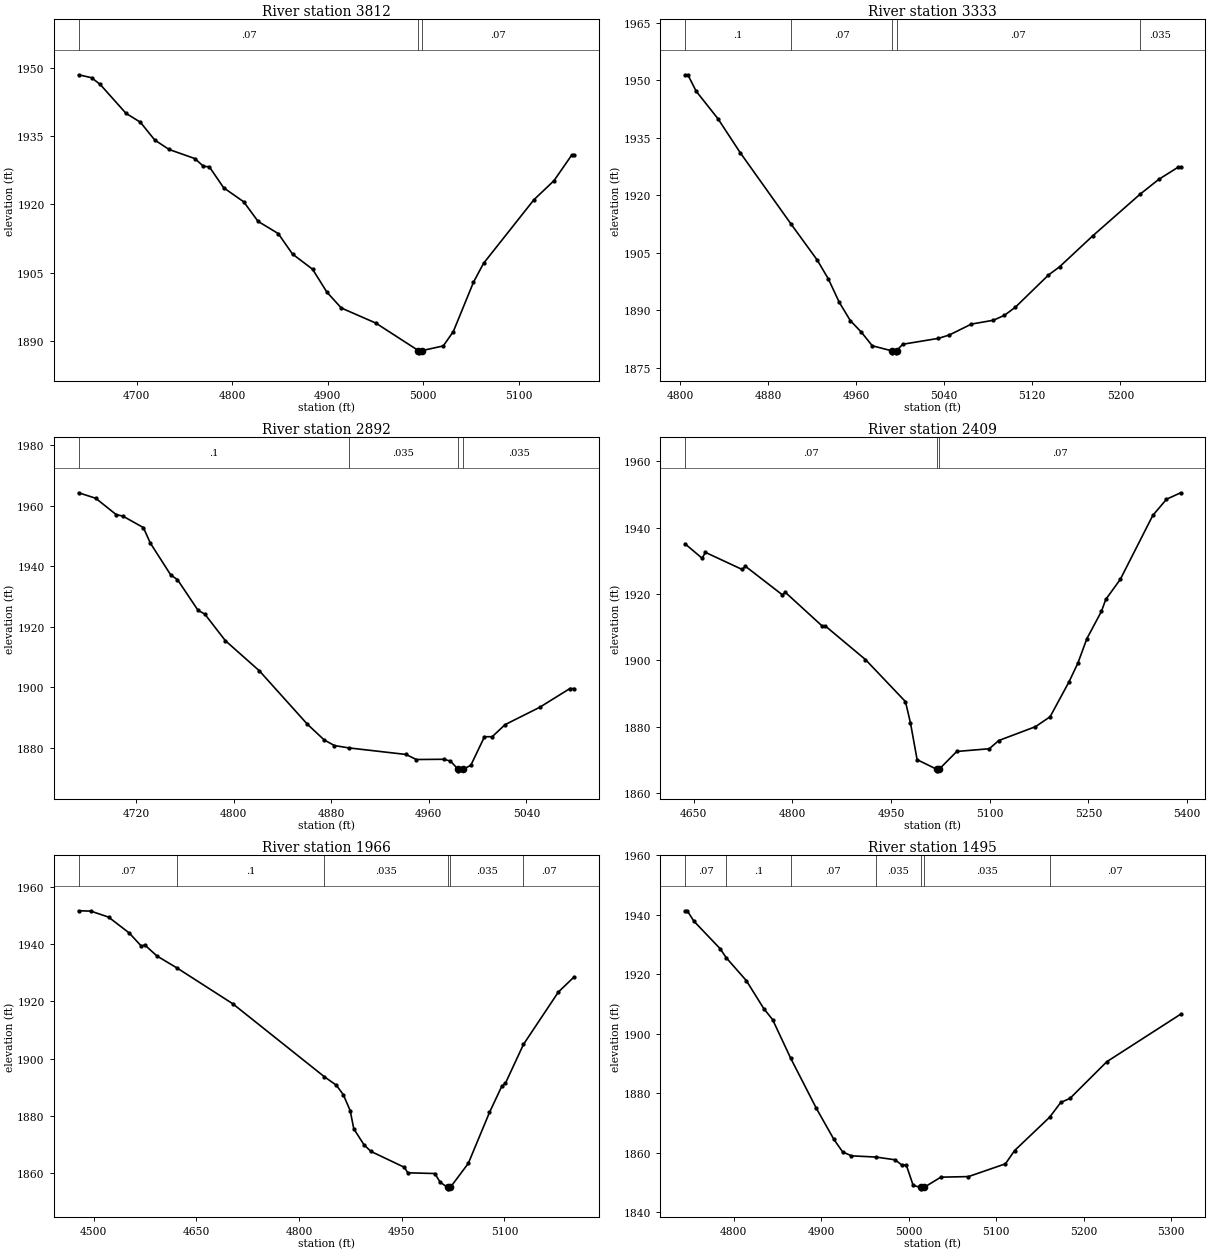
Type RM Length L Ch R = 1,3812,479,479,479
BEGIN DESCRIPTION:
Edmunson Creek 8.0
END DESCRIPTION:
XS GIS Cut Line= 3
      1853625.02     13913474.97      1853425.00     13913775.00
      1853475.00     13913924.99
#Sta/Elev= 30
  4639.3 1948.49  4652.9 1947.84  4661.9 1946.36  4688.9 1940.01  4703.9 1938.07
  4719.0 1934.14  4734.0 1932.07  4761.0 1930.07  4770.0 1928.36  4776.1 1928.27
  4791.1 1923.65  4812.1 1920.57  4827.1 1916.27  4848.2 1913.59  4863.2 1909.08
  4884.2 1905.74  4899.2 1900.70  4914.3 1897.22  4950.3 1893.92  4994.9 1887.87
  4995.1 1887.37  4998.9 1887.87  5021.0 1888.89  5031.5 1892.05  5052.6 1902.89
  5063.1 1907.03  5115.8 1921.01  5136.9 1925.22  5155.4 1930.83  5158.0 1930.83
#Mann=3,-1,0
  4639.3    0.07       0  4994.9    0.05       0  4998.9    0.07       0
Bank Sta=4994.9,4998.9
Exp/Cntr=0.3,0.1

Type RM Length L Ch R = 1,3333,441,441,441
BEGIN DESCRIPTION:
Edmunson Creek 7.0
END DESCRIPTION:
XS GIS Cut Line= 3
      1853025.00     13913375.04      1853025.00     13913575.00
      1853025.00     13913825.04
#Sta/Elev= 30
  4804.7 1951.45  4807.2 1951.45  4814.7 1947.19  4834.7 1939.93  4854.7 1931.16
  4900.7 1912.61  4924.7 1903.13  4934.7 1898.26  4944.7 1892.12  4954.7 1887.36
  4964.7 1884.35  4974.7 1880.78  4992.7 1879.44  4992.9 1878.94  4996.4 1878.94
  4996.7 1879.44  5002.2 1881.17  5034.7 1882.71  5044.7 1883.60  5064.7 1886.44
  5084.7 1887.44  5094.7 1888.73  5104.7 1890.86  5134.7 1899.24  5144.7 1901.36
  5174.7 1909.40  5217.8 1920.29  5234.7 1924.15  5252.2 1927.31  5254.7 1927.31
#Mann=5,-1,0
  4804.7     0.1       0  4900.7    0.07       0  4992.7    0.05       0
  4996.7    0.07       0  5217.8   0.035       0
Bank Sta=4992.7,4996.7
Exp/Cntr=0.3,0.1

Type RM Length L Ch R = 1,2892,483,483,483
BEGIN DESCRIPTION:
Edmunson Creek 6.0
END DESCRIPTION:
XS GIS Cut Line= 3
      1852575.00     13913425.01      1852725.00     13913725.00
      1852774.99     13913774.99
#Sta/Elev= 30
  4673.0 1964.27  4687.0 1962.46  4703.7 1957.08  4709.3 1956.55  4726.1 1952.76
  4731.7 1947.69  4748.5 1937.11  4754.0 1935.57  4770.8 1925.47  4776.4 1924.19
  4793.2 1915.43  4821.1 1905.45  4860.3 1887.87  4874.2 1882.62  4882.6 1880.76
  4894.2 1879.99  4941.3 1877.81  4949.7 1876.14  4972.1 1876.22  4977.7 1875.64
  4984.0 1872.90  4984.3 1872.40  4988.0 1872.90  4994.4 1874.23  5005.6 1883.67
  5011.9 1883.67  5022.5 1887.67  5050.8 1893.38  5075.6 1899.59  5079.1 1899.59
#Mann=4,-1,0
  4673.0     0.1       0  4894.2   0.035       0  4984.0   0.035       0
  4988.0   0.035       0
Bank Sta=4984,4988
Exp/Cntr=0.3,0.1

Type RM Length L Ch R = 1,2409,443,443,443
BEGIN DESCRIPTION:
Edmunson Creek 5.0
END DESCRIPTION:
XS GIS Cut Line= 3
      1852265.34     13913516.97      1852325.00     13913875.00
      1852575.01     13914175.01
#Sta/Elev= 30
  4636.8 1935.15  4662.7 1930.81  4667.7 1932.58  4723.5 1927.44  4728.6 1928.38
  4784.3 1919.85  4789.4 1920.51  4845.2 1910.40  4850.2 1910.37  4911.1 1900.27
  4971.9 1887.60  4979.5 1881.17  4989.6 1870.11  5019.2 1867.25  5019.5 1866.75
  5023.2 1867.25  5049.9 1872.59  5099.4 1873.41  5113.7 1875.88  5169.6 1880.06
  5191.8 1883.05  5220.4 1893.50  5234.1 1899.23  5247.7 1906.57  5269.9 1914.82
  5276.4 1918.39  5298.5 1924.43  5348.0 1943.73  5368.8 1948.59  5390.3 1950.54
#Mann=3,-1,0
  4636.8    0.07       0  5019.2    0.05       0  5023.2    0.07       0
Bank Sta=5019.2,5023.2
Exp/Cntr=0.3,0.1

Type RM Length L Ch R = 1,1966,471,471,471
BEGIN DESCRIPTION:
Edmunson Creek 4.0
END DESCRIPTION:
XS GIS Cut Line= 3
      1852042.21     13913411.72      1851975.00     13913925.00
      1851925.01     13914124.98
#Sta/Elev= 30
  4478.1 1951.67  4495.8 1951.56  4521.8 1949.46  4552.0 1943.91  4569.7 1939.32
  4574.7 1939.75  4592.4 1935.89  4622.2 1931.63  4703.3 1919.18  4837.1 1893.68
  4854.6 1890.72  4864.7 1887.42  4874.7 1881.88  4880.0 1875.50  4894.9 1869.92
  4905.0 1867.61  4953.8 1862.06  4958.9 1860.13  4998.3 1859.88  5006.1 1856.87
  5017.0 1855.03  5017.2 1854.53  5021.0 1855.03  5047.3 1863.44  5078.2 1881.22
  5096.3 1890.44  5101.4 1891.37  5127.8 1904.97  5178.7 1923.25  5201.9 1928.59
#Mann=6,-1,0
  4478.1    0.07       0  4622.2     0.1       0  4837.1   0.035       0
  5017.0   0.035       0  5021.0   0.035       0  5127.8    0.07       0
Bank Sta=5017,5021
Exp/Cntr=0.3,0.1

Type RM Length L Ch R = 1,1495,475,475,475
BEGIN DESCRIPTION:
Edmunson Creek 3.0
END DESCRIPTION:
XS GIS Cut Line= 3
      1851575.00     13913474.98      1851575.00     13913725.00
      1851674.99     13914024.96
#Sta/Elev= 30
  4744.6 1941.37  4747.1 1941.37  4754.6 1937.89  4784.6 1928.64  4791.7 1925.55
  4814.6 1917.88  4834.6 1908.44  4844.6 1904.78  4865.3 1891.77  4894.6 1874.95
  4914.6 1864.53  4924.6 1860.32  4934.6 1859.00  4962.8 1858.58  4984.6 1857.66
  4992.1 1855.93  4997.3 1855.93  5005.2 1849.06  5013.7 1848.40  5013.9 1847.90
  5017.7 1848.40  5036.8 1851.82  5068.4 1852.02  5110.6 1856.31  5121.1 1860.77
  5161.2 1872.00  5173.8 1876.93  5184.4 1878.31  5226.5 1890.65  5310.8 1906.60
#Mann=7,-1,0
  4744.6    0.07       0  4791.7     0.1       0  4865.3    0.07       0
  4962.8   0.035       0  5013.7   0.035       0  5017.7   0.035       0
  5161.2    0.07       0
Bank Sta=5013.7,5017.7
Exp/Cntr=0.3,0.1

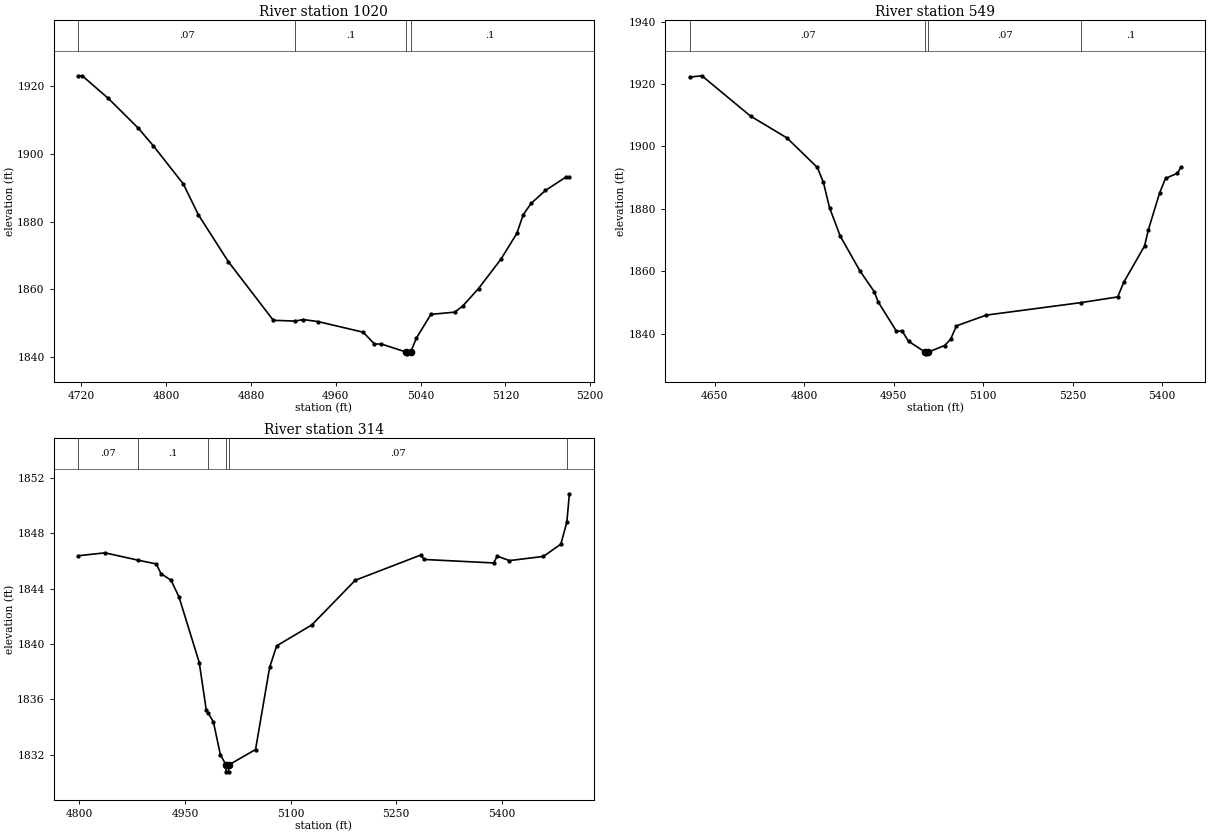
Type RM Length L Ch R = 1,1020,471,471,471
BEGIN DESCRIPTION:
Edmunson Creek 2.0
END DESCRIPTION:
XS GIS Cut Line= 3
      1851024.98     13913824.98      1851225.00     13914025.00
      1851375.04     13914125.03
#Sta/Elev= 30
  4717.1 1923.13  4720.7 1923.13  4745.4 1916.42  4773.7 1907.62  4787.8 1902.44
  4816.1 1891.16  4830.3 1882.05  4858.6 1868.19  4901.0 1850.87  4921.5 1850.66
  4929.3 1851.10  4943.4 1850.49  4985.8 1847.36  4996.4 1843.87  5003.0 1843.87
  5026.5 1841.47  5026.8 1840.97  5030.5 1841.47  5036.0 1845.64  5049.6 1852.63
  5072.1 1853.29  5079.6 1855.07  5094.6 1860.27  5115.7 1868.94  5130.7 1876.54
  5136.7 1882.06  5144.2 1885.43  5157.7 1889.24  5177.2 1893.24  5180.3 1893.24
#Mann=4,-1,0
  4717.1    0.07       0  4921.5     0.1       0  5026.5    0.05       0
  5030.5     0.1       0
Bank Sta=5026.5,5030.5
Exp/Cntr=0.3,0.1

Type RM Length L Ch R = 1,549,235,235,235
BEGIN DESCRIPTION:
Edmunson Creek 1.0
END DESCRIPTION:
XS GIS Cut Line= 3
      1850851.90     13913945.24      1850925.00     13914325.00
      1851360.72     13914307.68
#Sta/Elev= 30
  4608.6 1922.22  4628.7 1922.63  4710.2 1909.71  4771.3 1902.70  4822.2 1893.24
  4832.4 1888.43  4842.6 1880.34  4860.5 1871.25  4893.5 1860.10  4917.5 1853.43
  4924.1 1850.14  4954.6 1840.79  4964.3 1840.78  4975.0 1837.50  5003.3 1833.98
  5003.6 1833.48  5007.3 1833.98  5035.4 1836.14  5045.4 1838.12  5055.4 1842.46
  5105.4 1845.90  5264.6 1849.92  5325.6 1851.73  5335.6 1856.40  5370.6 1868.09
  5376.9 1873.24  5395.7 1885.02  5405.7 1889.72  5425.7 1891.38  5431.4 1893.36
#Mann=4,-1,0
  4608.6    0.07       0  5003.3    0.05       0  5007.3    0.07       0
  5264.6     0.1       0
Bank Sta=5003.3,5007.3
Exp/Cntr=0.3,0.1

Type RM Length L Ch R = 1,314,0,0,0
BEGIN DESCRIPTION:
Edmunson Creek 0.0
END DESCRIPTION:
XS GIS Cut Line= 4
      1850740.18     13914499.09      1850842.21     13914560.32
      1851090.16     13914556.39      1851406.62     13914459.60
#Sta/Elev= 30
  4798.5 1846.37  4836.2 1846.58  4883.3 1846.05  4909.1 1845.78  4915.9 1845.08
  4930.3 1844.60  4941.6 1843.38  4970.3 1838.66  4980.3 1835.22  4982.4 1835.05
  4990.3 1834.40  5000.3 1832.02  5008.3 1831.28  5008.5 1830.78  5012.0 1830.78
  5012.3 1831.28  5050.3 1832.39  5070.3 1838.31  5080.3 1839.87  5130.3 1841.38
  5192.0 1844.60  5285.1 1846.42  5290.3 1846.10  5388.7 1845.85  5393.9 1846.34
  5411.1 1846.02  5459.5 1846.32  5484.3 1847.21  5492.8 1848.81  5496.4 1850.84
#Mann=6,-1,0
  4798.5    0.07       0  4883.3     0.1       0  4982.4    0.07       0
  5008.3    0.05       0  5012.3    0.07       0  5492.8     0.1       0
Bank Sta=5008.3,5012.3
Exp/Cntr=0.3,0.1

Chan Stop Cuts=-1