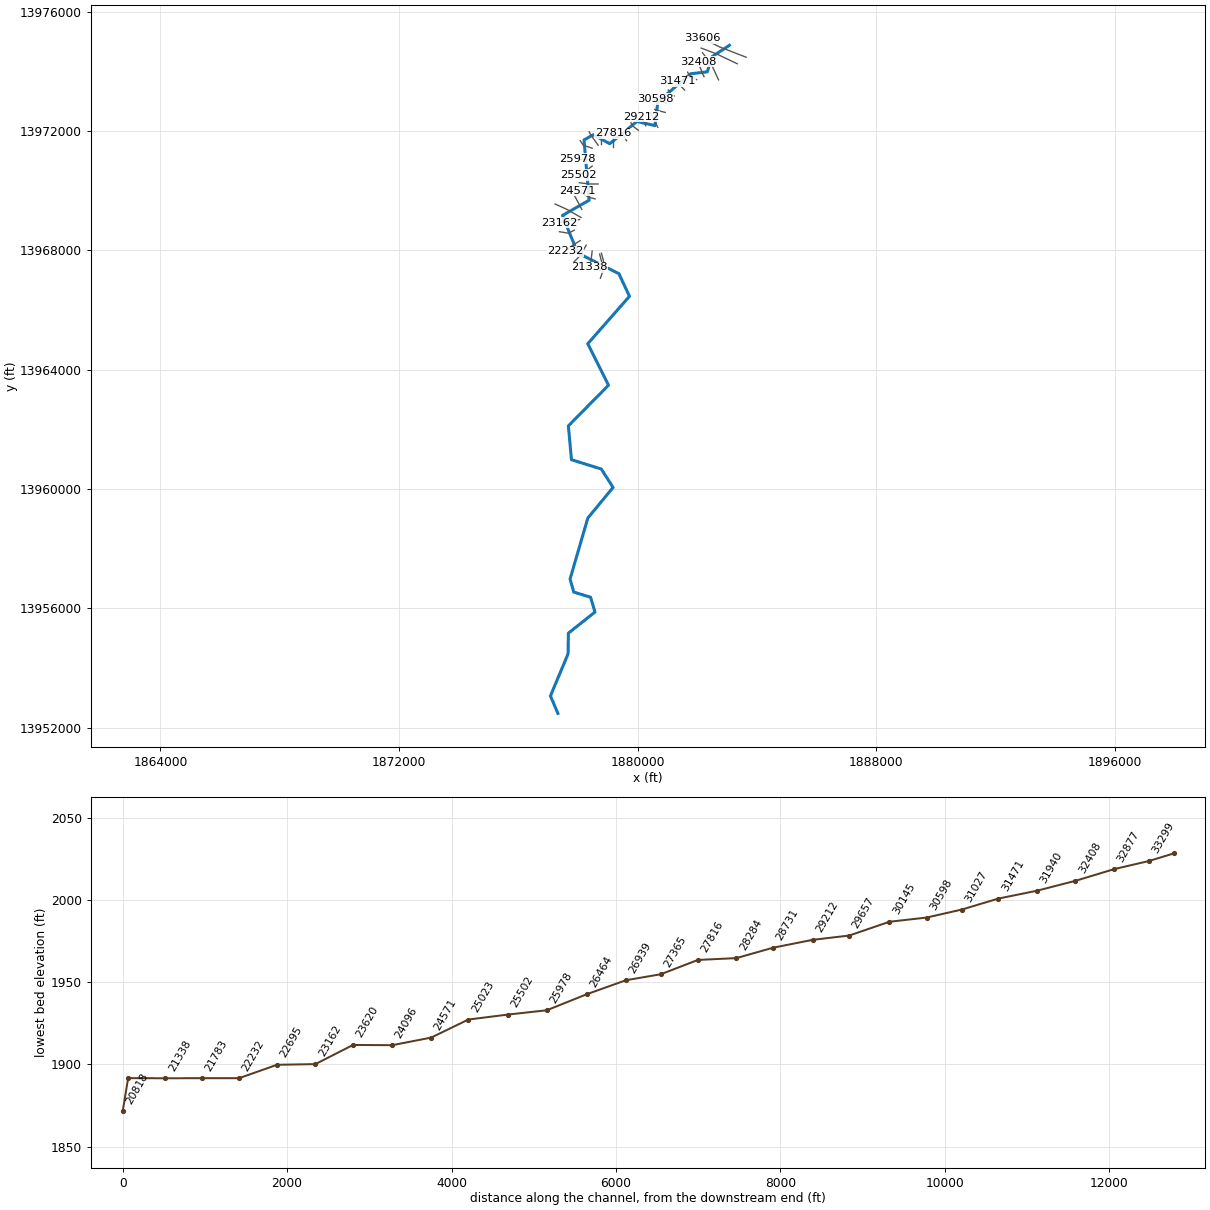
--- Fall Branch.prj (project) ---

Proj Title=Fall Branch Base Level Engineering
Current Plan=p01
Default Exp/Contr=0.3,0.1
English Units
Geom File=g01
Flow File=f01
Plan File=p01
BEGIN DESCRIPTION:
Fall Branch
END DESCRIPTION:

--- Fall Branch.p01 (plan) ---

Plan Title=Multiple Run
Short Identifier=Multiple
Geom File=g01
Flow File=f01
Subcritical Flow
K Sum by GR= 0
Std Step Tol= 0.01
Critical Tol= 0.01
Num of Std Step Trials= 20
Max Error Tol= 0.3
Flow Tol Ratio= 0.001
Split Flow NTrial= 30
Split Flow Tol= 0.02
Split Flow Ratio= 0.02
Log Output Level= 0
Friction Slope Method= 1
Unsteady Friction Slope Method= 2
Unsteady Bridges Friction Slope Method= 1
Parabolic Critical Depth
Global Vel Dist=  1 , 1 , 1
Global Log Level= 0
CheckData=True
Encroach Param= -1, 0, 0, 0
BEGIN DESCRIPTION:
Multiple Run
END DESCRIPTION:

--- Fall Branch.f01 (steady flow) ---

Flow Title=Multiple
Number of Profiles=7
Profile Names=10-year,25-year,50-year,1pct_min,100-year,1pct_plu,500-year
River Rch & RM= Fall Branch,Reach-1,33606
    1550    2688    3787    2574    5136   10248    9340
River Rch & RM= Fall Branch,Reach-1,30145
    2947    5277    7595    5263   10501   20952   19861
River Rch & RM= Fall Branch,Reach-1,23620
    3255    5857    8457    5877   11726   23397   22307
River Rch & RM= Fall Branch,Reach-1,20434
    5439    9977   14594   10257   20466   40836   39830
River Rch & RM= Fall Branch,Reach-1,13698
    5637   10343   15131   10634   21218   42335   41286
River Rch & RM= Fall Branch,Reach-1,10391
    6257   11497   16833   11835   23614   47116   45986
River Rch & RM= Fall Branch,Reach-1,4546
    6609   12160   17820   12539   25018   49918   48793
Boundary for River Rch & Prof#=Fall Branch,Reach-1,1
Up Type=0
Dn Type=3
Dn Slope=0.005
Boundary for River Rch & Prof#=Fall Branch,Reach-1,2
Up Type=0
Dn Type=3
Dn Slope=0.005
Boundary for River Rch & Prof#=Fall Branch,Reach-1,3
Up Type=0
Dn Type=3
Dn Slope=0.005
Boundary for River Rch & Prof#=Fall Branch,Reach-1,4
Up Type=0
Dn Type=3
Dn Slope=0.005
Boundary for River Rch & Prof#=Fall Branch,Reach-1,5
Up Type=0
Dn Type=3
Dn Slope=0.005
Boundary for River Rch & Prof#=Fall Branch,Reach-1,6
Up Type=0
Dn Type=3
Dn Slope=0.005
Boundary for River Rch & Prof#=Fall Branch,Reach-1,7
Up Type=0
Dn Type=3
Dn Slope=0.005

--- Fall Branch.g01 (geometry) ---

Geom Title=Existing Conditions

River Reach=Fall Branch,Reach-1
Reach XY= 30
      1883075.00     13974875.00      1882488.37     13974488.32
      1882335.11     13973985.38      1881772.55     13973919.54
      1880675.00     13972975.00      1880581.21     13972182.80
      1879976.47     13972321.47      1879064.31     13971575.77
      1878509.78     13971874.51      1878201.17     13971701.87
      1878372.94     13969680.85      1877477.24     13969169.07
      1877988.40     13967911.70      1879369.39     13967219.39
      1879725.44     13966459.82      1878327.26     13964869.06
      1879021.25     13963476.55      1877676.19     13962114.52
      1877780.59     13960980.61      1878781.05     13960667.50
      1879175.24     13960049.92      1878328.61     13959023.50
      1877733.07     13956978.31      1877857.86     13956541.27
      1878419.74     13956369.53      1878568.43     13955875.00
      1877676.62     13955163.42      1877666.98     13954471.69
      1877075.51     13953059.79      1877325.00     13952475.00

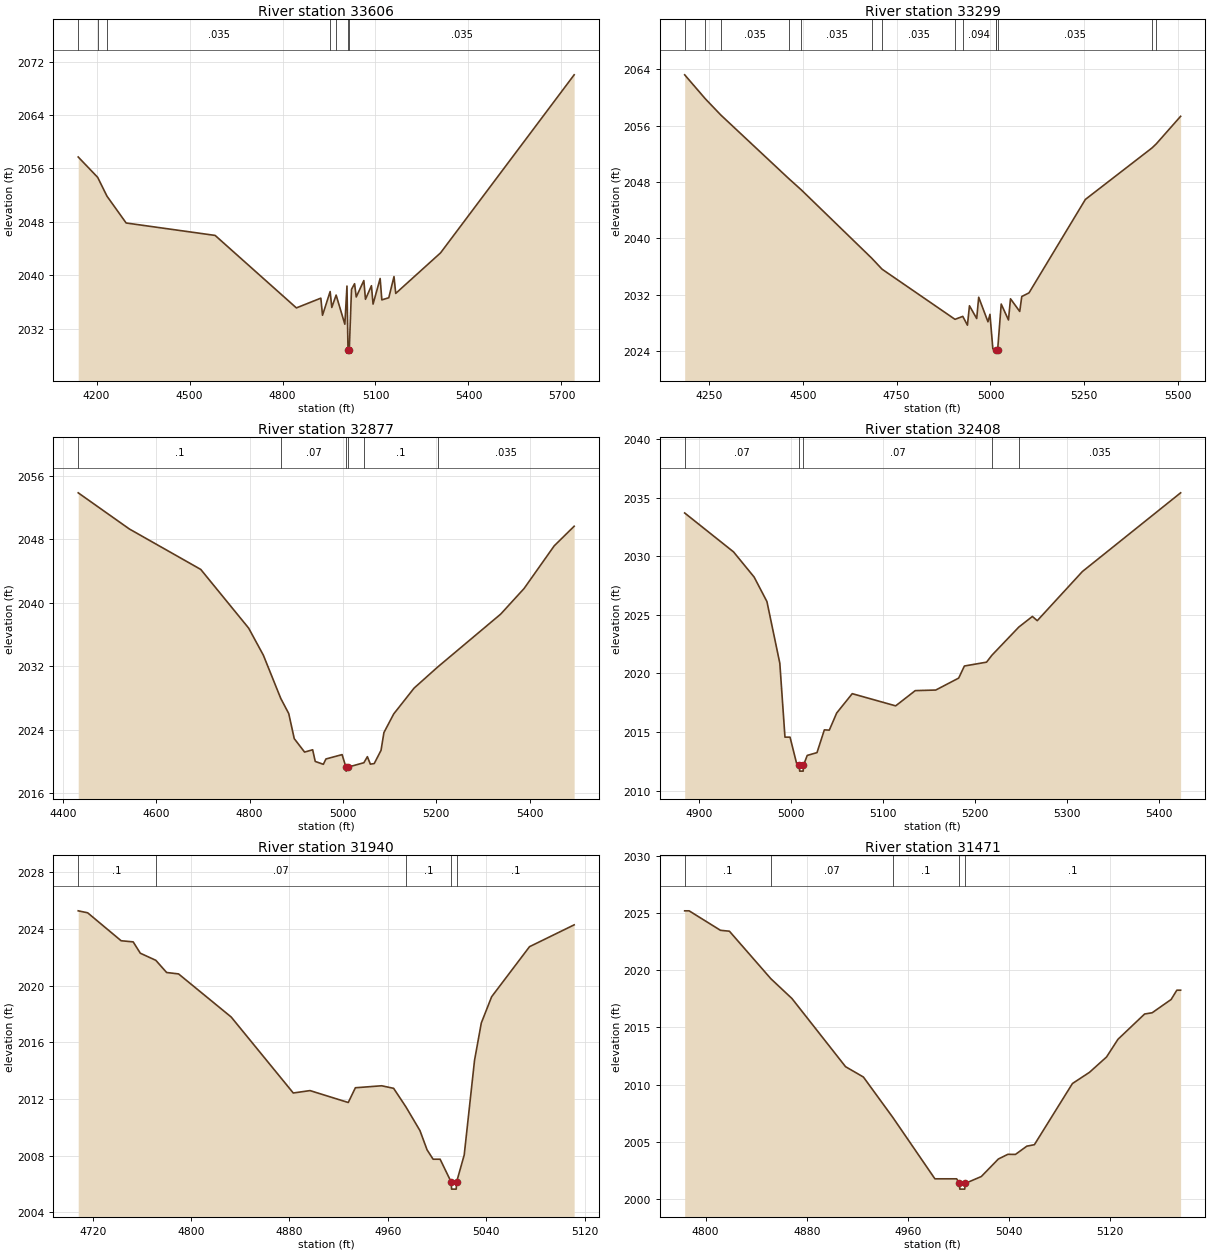
Type RM Length L Ch R = 1,33606,307,307,307
BEGIN DESCRIPTION:
Fall Branch 69.0
END DESCRIPTION:
XS GIS Cut Line= 3
      1883636.70     13974474.85      1882746.17     13974821.56
      1882169.08     13975108.64
#Sta/Elev= 30
  4140.8 2057.71  4203.5 2054.67  4233.7 2051.84  4295.5 2047.83  4582.6 2045.97
  4844.8 2035.12  4923.7 2036.58  4929.1 2034.02  4953.7 2037.57  4959.0 2035.19
  4973.0 2037.04  5001.1 2032.68  5008.0 2038.39  5011.3 2028.85  5011.5 2028.35
  5015.4 2028.85  5022.6 2037.90  5032.5 2038.74  5037.9 2036.76  5062.4 2039.21
  5067.7 2036.41  5086.9 2038.44  5092.2 2035.69  5115.0 2039.52  5120.5 2036.32
  5142.9 2036.64  5159.7 2039.81  5165.3 2037.29  5310.0 2043.36  5741.0 2070.01
#Mann=7,-1,0
  4140.8   0.035       0  4203.5   0.063       0  4233.7   0.035       0
  4953.7   0.063       0  4973.0   0.035       0  5011.3   0.035       0
  5015.4   0.035       0
Bank Sta=5011.3,5015.4
Exp/Cntr=0.3,0.1

Type RM Length L Ch R = 1,33299,422,422,422
BEGIN DESCRIPTION:
Fall Branch 68.0
END DESCRIPTION:
XS GIS Cut Line= 3
      1883338.65     13974256.58      1882660.68     13974578.35
      1882128.23     13974783.06
#Sta/Elev= 30
  4185.5 2063.22  4240.4 2059.82  4281.6 2057.52  4462.1 2048.51  4496.5 2046.86
  4683.8 2037.17  4711.3 2035.61  4905.5 2028.49  4926.2 2028.91  4938.6 2027.66
  4944.0 2030.42  4963.3 2028.60  4968.6 2031.63  4993.3 2028.14  4998.6 2029.20
  5006.3 2024.30  5013.6 2024.21  5014.9 2024.19  5015.2 2023.69  5019.1 2024.19
  5028.6 2030.66  5047.9 2028.40  5053.3 2031.41  5077.9 2029.61  5083.3 2031.73
  5102.6 2032.25  5252.7 2045.52  5430.3 2052.84  5441.5 2053.41  5506.4 2057.33
#Mann=14,-1,0
  4185.5   0.035       0  4240.4     0.1       0  4281.6   0.035       0
  4462.1    0.07       0  4496.5   0.035       0  4683.8    0.07       0
  4711.3   0.035       0  4905.5    0.07       0  4926.2   0.094       0
  5013.6   0.035       0  5014.9    0.05       0  5019.1   0.035       0
  5430.3   0.094       0  5441.5   0.035       0
Bank Sta=5014.9,5019.1
Exp/Cntr=0.3,0.1

Type RM Length L Ch R = 1,32877,469,469,469
BEGIN DESCRIPTION:
Fall Branch 67.0
END DESCRIPTION:
XS GIS Cut Line= 3
      1882712.71     13973715.85      1882475.00     13974225.00
      1882175.01     13974624.99
#Sta/Elev= 30
  4433.2 2053.82  4542.6 2049.27  4695.6 2044.17  4798.1 2036.78  4829.6 2033.37
  4866.9 2027.92  4884.0 2026.01  4895.8 2022.85  4917.9 2021.16  4935.2 2021.45
  4940.7 2019.98  4958.1 2019.62  4963.6 2020.29  4998.2 2020.84  5006.5 2019.26
  5006.8 2018.76  5010.8 2019.26  5044.9 2019.82  5052.4 2020.58  5058.7 2019.64
  5067.0 2019.71  5081.6 2021.38  5087.8 2023.62  5108.7 2025.96  5152.4 2029.22
  5202.6 2031.86  5337.8 2038.54  5387.8 2041.76  5452.4 2047.14  5495.1 2049.61
#Mann=6,-1,0
  4433.2     0.1       0  4866.9    0.07       0  5006.5    0.05       0
  5010.8    0.07       0  5044.9     0.1       0  5202.6   0.035       0
Bank Sta=5006.5,5010.8
Exp/Cntr=0.3,0.1

Type RM Length L Ch R = 1,32408,468,468,468
BEGIN DESCRIPTION:
Fall Branch 66.0
END DESCRIPTION:
XS GIS Cut Line= 3
      1882225.00     13973825.00      1882175.00     13973925.00
      1882025.00     13974325.00
#Sta/Elev= 30
  4884.1 2033.69  4937.2 2030.37  4959.6 2028.22  4973.5 2026.13  4987.5 2020.87
  4993.1 2014.56  4998.6 2014.56  5005.7 2012.33  5008.8 2012.16  5009.1 2011.66
  5012.9 2011.66  5013.2 2012.16  5017.3 2013.00  5027.9 2013.24  5035.9 2015.18
  5041.3 2015.16  5049.3 2016.62  5066.2 2018.27  5113.4 2017.23  5134.7 2018.53
  5157.0 2018.58  5181.9 2019.60  5188.1 2020.63  5212.2 2020.96  5218.0 2021.55
  5247.2 2023.95  5262.0 2024.86  5267.3 2024.50  5316.3 2028.69  5423.1 2035.41
#Mann=5,-1,0
  4884.1    0.07       0  5008.8    0.05       0  5013.2    0.07       0
  5218.0     0.1       0  5247.2   0.035       0
Bank Sta=5008.8,5013.2
Exp/Cntr=0.3,0.1

Type RM Length L Ch R = 1,31940,469,469,469
BEGIN DESCRIPTION:
Fall Branch 65.0
END DESCRIPTION:
XS GIS Cut Line= 3
      1881974.97     13973725.02      1881725.00     13973875.00
      1881675.01     13973974.99
#Sta/Elev= 30
  4708.2 2025.27  4715.9 2025.13  4743.1 2023.16  4752.9 2023.08  4758.7 2022.28
  4771.3 2021.78  4780.1 2020.92  4789.8 2020.82  4832.6 2017.78  4883.1 2012.42
  4896.7 2012.59  4927.8 2011.75  4933.6 2012.79  4955.0 2012.93  4964.7 2012.75
  4974.7 2011.44  4986.1 2009.77  4991.9 2008.41  4996.8 2007.75  5002.5 2007.75
  5011.5 2006.14  5011.8 2005.64  5015.6 2005.64  5015.9 2006.14  5022.1 2008.05
  5030.5 2014.73  5036.0 2017.36  5044.4 2019.21  5075.2 2022.74  5111.5 2024.28
#Mann=5,-1,0
  4708.2     0.1       0  4771.3    0.07       0  4974.7     0.1       0
  5011.5    0.05       0  5015.9     0.1       0
Bank Sta=5011.5,5015.9
Exp/Cntr=0.3,0.1

Type RM Length L Ch R = 1,31471,444,444,444
BEGIN DESCRIPTION:
Fall Branch 64.0
END DESCRIPTION:
XS GIS Cut Line= 3
      1881575.01     13973374.99      1881425.00     13973525.00
      1881325.01     13973674.98
#Sta/Elev= 30
  4783.4 2025.17  4786.9 2025.17  4811.7 2023.47  4818.8 2023.39  4851.6 2019.24
  4868.3 2017.51  4910.7 2011.56  4924.8 2010.66  4948.1 2007.13  4981.4 2001.77
  4998.6 2001.77  5000.8 2001.37  5001.1 2000.87  5005.0 2000.87  5005.4 2001.37
  5018.1 2001.97  5031.6 2003.50  5039.1 2003.91  5045.1 2003.90  5054.1 2004.62
  5060.1 2004.75  5090.2 2010.09  5103.7 2011.07  5117.2 2012.41  5126.2 2013.95
  5147.3 2016.16  5153.3 2016.27  5168.3 2017.43  5172.8 2018.24  5175.8 2018.24
#Mann=5,-1,0
  4783.4     0.1       0  4851.6    0.07       0  4948.1     0.1       0
  5000.8    0.05       0  5005.4     0.1       0
Bank Sta=5000.8,5005.4
Exp/Cntr=0.3,0.1

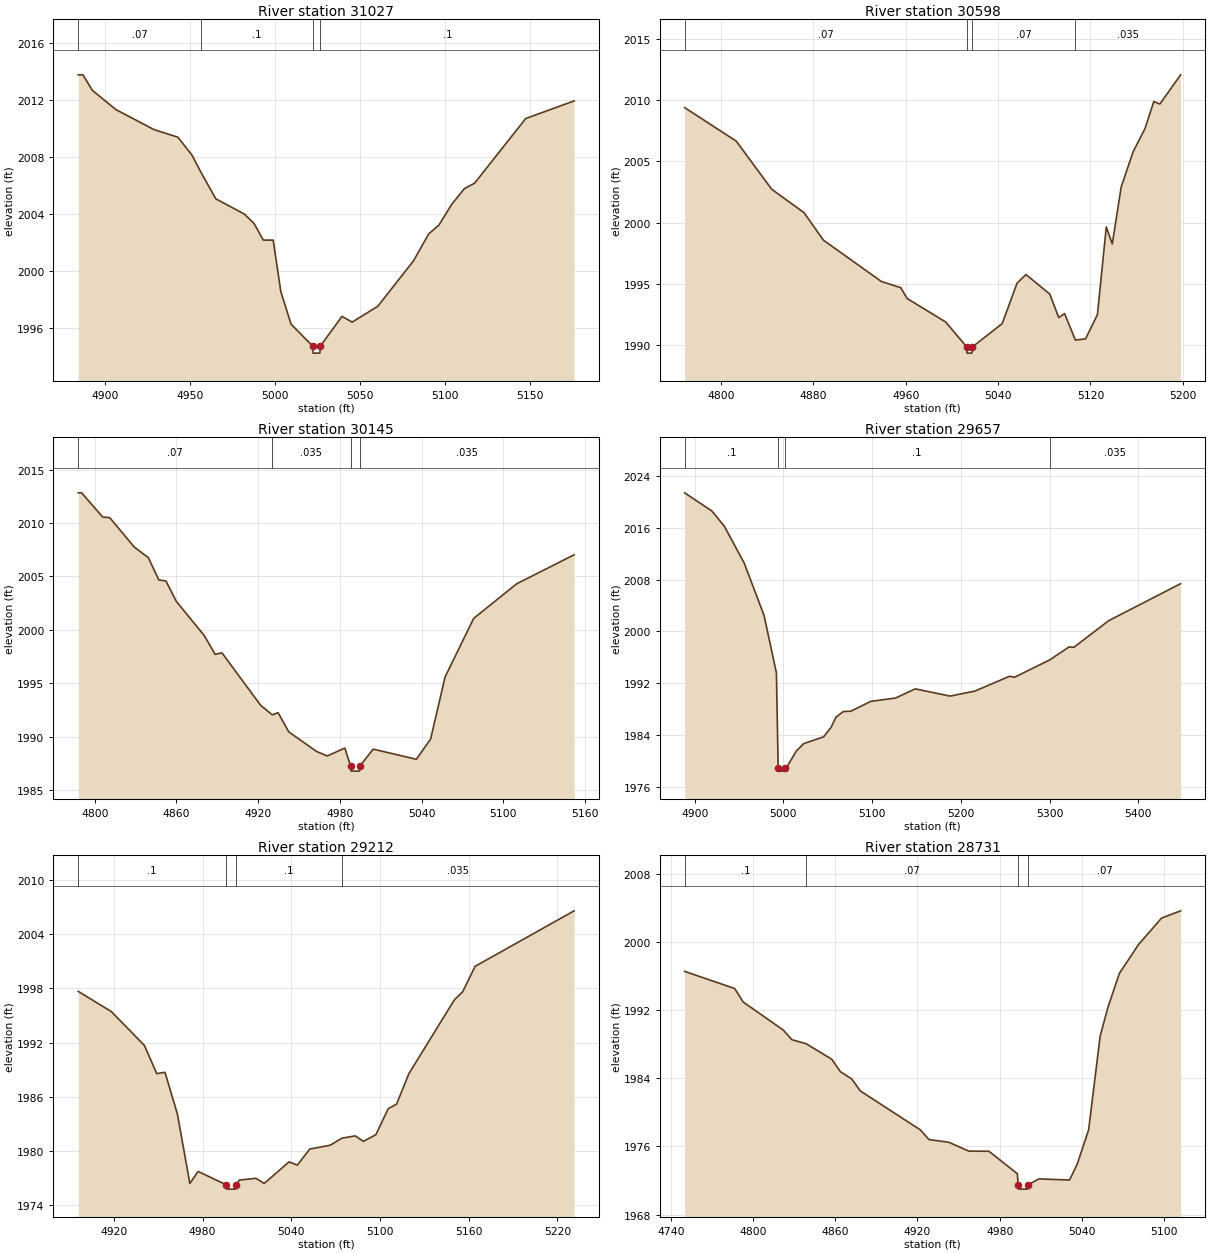
Type RM Length L Ch R = 1,31027,429,429,429
BEGIN DESCRIPTION:
Fall Branch 63.0
END DESCRIPTION:
XS GIS Cut Line= 3
      1881224.96     13973175.02      1881125.00     13973225.00
      1881025.02     13973374.97
#Sta/Elev= 30
  4884.2 2013.76  4887.0 2013.76  4892.5 2012.67  4906.5 2011.31  4928.9 2009.91
  4942.9 2009.38  4951.2 2008.12  4956.4 2006.93  4965.2 2005.05  4982.0 2003.98
  4987.6 2003.34  4993.2 2002.15  4999.0 2002.15  5003.5 1998.53  5009.5 1996.25
  5022.2 1994.71  5022.5 1994.21  5026.5 1994.21  5026.8 1994.71  5039.5 1996.79
  5045.5 1996.39  5060.6 1997.50  5081.6 2000.69  5090.6 2002.59  5096.6 2003.21
  5104.1 2004.66  5111.6 2005.77  5117.6 2006.15  5147.7 2010.69  5176.2 2011.93
#Mann=4,-1,0
  4884.2    0.07       0  4956.4     0.1       0  5022.2    0.05       0
  5026.8     0.1       0
Bank Sta=5022.2,5026.8
Exp/Cntr=0.3,0.1

Type RM Length L Ch R = 1,30598,453,453,453
BEGIN DESCRIPTION:
Fall Branch 62.0
END DESCRIPTION:
XS GIS Cut Line= 3
      1880974.97     13972925.01      1880775.00     13973025.00
      1880575.03     13973074.99
#Sta/Elev= 30
  4768.4 2009.39  4813.1 2006.65  4843.8 2002.72  4871.8 2000.81  4888.6 1998.56
  4938.9 1995.18  4955.6 1994.68  4961.2 1993.79  4994.6 1991.87  5012.8 1989.83
  5013.1 1989.33  5017.2 1989.33  5017.6 1989.83  5043.5 1991.74  5056.4 1995.05
  5064.1 1995.75  5084.7 1994.16  5092.5 1992.24  5097.6 1992.56  5106.9 1990.40
  5115.7 1990.49  5126.0 1992.47  5133.7 1999.64  5138.9 1998.25  5146.6 2002.90
  5156.9 2005.77  5167.2 2007.67  5174.9 2009.89  5180.1 2009.68  5198.1 2012.07
#Mann=4,-1,0
  4768.4    0.07       0  5012.8    0.05       0  5017.6    0.07       0
  5106.9   0.035       0
Bank Sta=5012.8,5017.6
Exp/Cntr=0.3,0.1

Type RM Length L Ch R = 1,30145,488,488,488
BEGIN DESCRIPTION:
Fall Branch 61.0
END DESCRIPTION:
XS GIS Cut Line= 3
      1880924.95     13972625.01      1880725.00     13972675.00
      1880575.02     13972724.99
#Sta/Elev= 30
  4787.9 2012.82  4790.4 2012.82  4805.9 2010.55  4811.0 2010.50  4829.1 2007.74
  4839.4 2006.75  4847.1 2004.66  4852.3 2004.57  4860.0 2002.65  4880.6 1999.43
  4888.4 1997.70  4893.5 1997.83  4921.9 1992.92  4930.4 1992.03  4934.7 1992.23
  4942.5 1990.44  4963.1 1988.59  4970.8 1988.18  4983.7 1988.92  4987.9 1987.26
  4988.4 1986.76  4994.4 1986.76  4994.9 1987.26  5004.5 1988.82  5036.2 1987.87
  5046.7 1989.76  5057.3 1995.57  5078.3 2001.06  5110.0 2004.31  5152.1 2007.02
#Mann=4,-1,0
  4787.9    0.07       0  4930.4   0.035       0  4987.9   0.035       0
  4994.9   0.035       0
Bank Sta=4987.9,4994.9
Exp/Cntr=0.3,0.1

Type RM Length L Ch R = 1,29657,445,445,445
BEGIN DESCRIPTION:
Fall Branch 60.0
END DESCRIPTION:
XS GIS Cut Line= 3
      1880675.01     13972124.99      1880625.00     13972225.00
      1880425.01     13972624.97
#Sta/Elev= 30
  4888.7 2021.46  4919.5 2018.63  4933.4 2016.29  4955.8 2010.59  4978.2 2002.47
  4992.1 1993.60  4994.1 1978.89  4994.6 1978.39  5000.8 1978.39  5001.3 1978.89
  5003.3 1978.89  5014.5 1981.49  5022.9 1982.65  5045.2 1983.69  5053.6 1985.14
  5059.2 1986.73  5067.6 1987.62  5076.0 1987.66  5098.3 1989.18  5126.3 1989.70
  5148.7 1991.12  5187.8 1990.00  5215.7 1990.77  5254.9 1993.07  5260.5 1992.92
  5300.0 1995.59  5322.0 1997.61  5327.5 1997.56  5366.7 2001.68  5447.7 2007.40
#Mann=4,-1,0
  4888.7     0.1       0  4994.1    0.05       0  5001.3     0.1       0
  5300.0   0.035       0
Bank Sta=4994.1,5001.3
Exp/Cntr=0.3,0.1

Type RM Length L Ch R = 1,29212,481,481,481
BEGIN DESCRIPTION:
Fall Branch 59.0
END DESCRIPTION:
XS GIS Cut Line= 3
      1880275.01     13972174.97      1880225.00     13972275.00
      1880125.02     13972474.96
#Sta/Elev= 30
  4895.9 1997.68  4918.3 1995.44  4940.7 1991.68  4949.0 1988.57  4954.6 1988.71
  4963.0 1984.08  4971.4 1976.40  4977.0 1977.73  4995.7 1976.27  4996.2 1975.77
  5002.4 1975.77  5002.9 1976.27  5004.9 1976.77  5016.1 1976.97  5021.7 1976.40
  5038.5 1978.79  5044.1 1978.43  5052.5 1980.21  5066.4 1980.64  5074.2 1981.41
  5083.2 1981.67  5088.8 1981.06  5097.2 1981.80  5105.6 1984.69  5111.2 1985.18
  5119.5 1988.55  5150.3 1996.74  5155.9 1997.63  5164.3 2000.45  5231.3 2006.60
#Mann=4,-1,0
  4895.9     0.1       0  4995.7    0.05       0  5002.9     0.1       0
  5074.2   0.035       0
Bank Sta=4995.7,5002.9
Exp/Cntr=0.3,0.1

Type RM Length L Ch R = 1,28731,447,447,447
BEGIN DESCRIPTION:
Fall Branch 58.0
END DESCRIPTION:
XS GIS Cut Line= 3
      1880025.02     13972024.98      1879825.00     13972175.00
      1879775.01     13972274.97
#Sta/Elev= 30
  4750.2 1996.55  4786.7 1994.54  4792.9 1992.95  4822.1 1989.67  4828.4 1988.53
  4838.8 1988.06  4857.5 1986.24  4863.8 1984.78  4872.1 1983.92  4878.4 1982.51
  4922.1 1977.95  4928.4 1976.81  4942.9 1976.49  4957.5 1975.45  4972.1 1975.44
  4992.9 1972.80  4993.5 1971.49  4994.0 1970.99  5000.2 1970.99  5000.7 1971.49
  5008.6 1972.19  5031.0 1972.06  5036.6 1973.94  5044.9 1977.96  5053.3 1988.95
  5058.9 1992.28  5067.3 1996.31  5081.3 1999.70  5098.1 2002.81  5112.0 2003.66
#Mann=4,-1,0
  4750.2     0.1       0  4838.8    0.07       0  4993.5    0.05       0
  5000.7    0.07       0
Bank Sta=4993.5,5000.7
Exp/Cntr=0.3,0.1

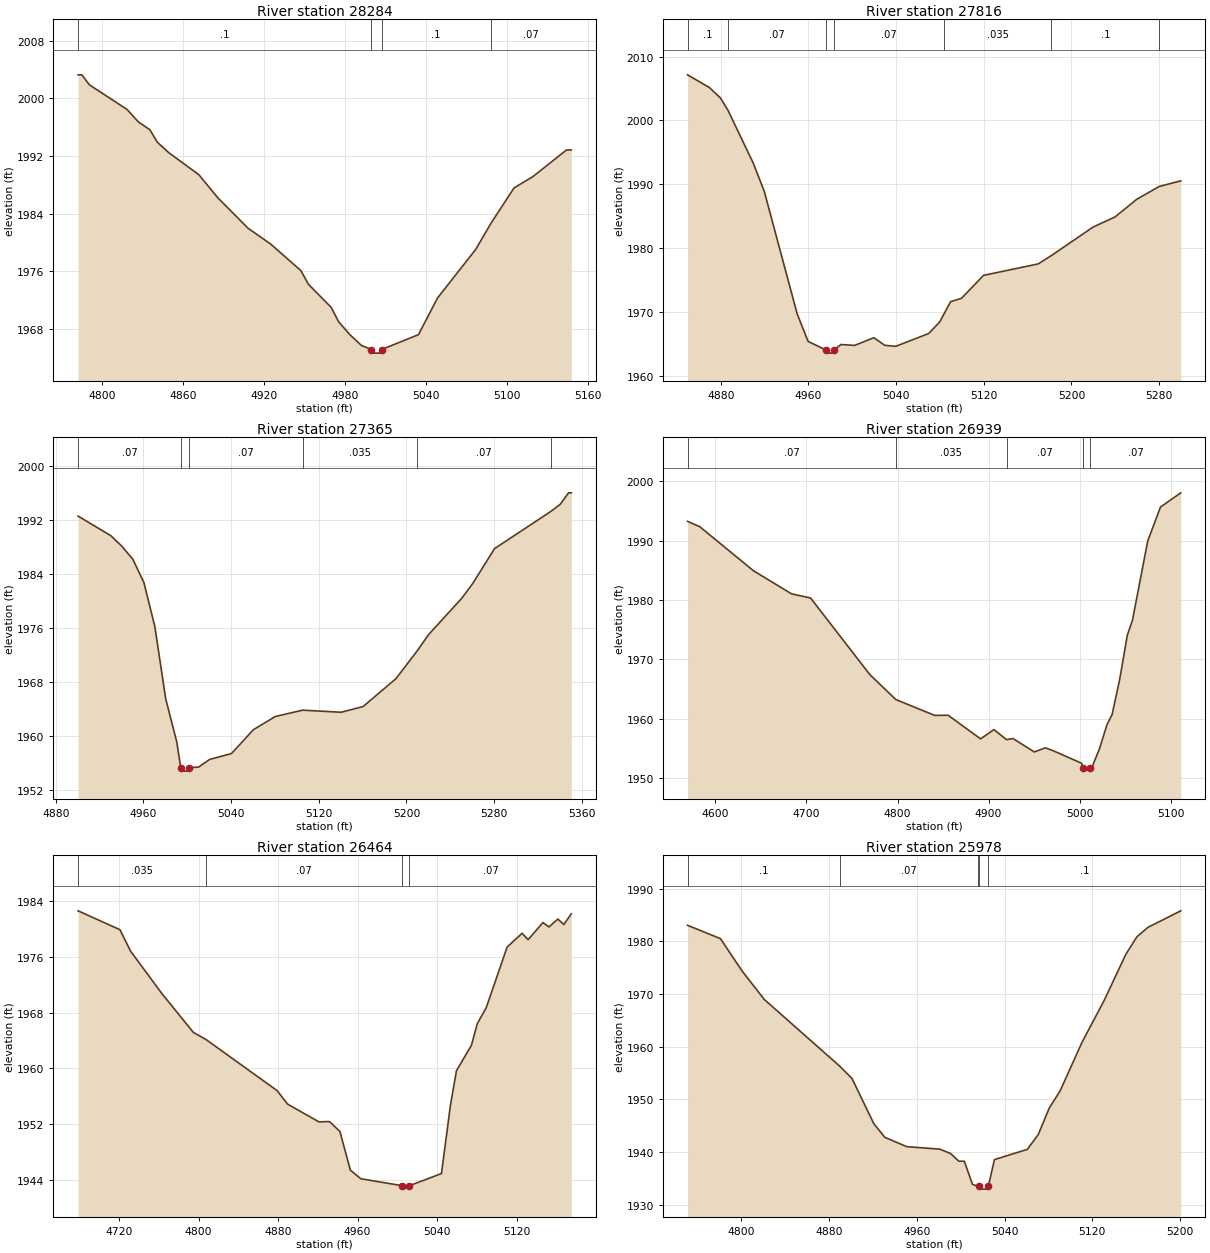
Type RM Length L Ch R = 1,28284,468,468,468
BEGIN DESCRIPTION:
Fall Branch 57.0
END DESCRIPTION:
XS GIS Cut Line= 3
      1879625.00     13971675.00      1879525.00     13971875.00
      1879425.02     13971974.98
#Sta/Elev= 30
  4782.5 2003.28  4785.3 2003.28  4790.9 2001.89  4818.8 1998.47  4827.2 1996.73
  4835.6 1995.67  4841.2 1993.92  4849.6 1992.48  4871.9 1989.42  4885.9 1986.22
  4908.3 1981.99  4925.0 1979.80  4947.4 1976.11  4953.0 1974.21  4969.8 1971.01
  4975.4 1968.99  4983.7 1967.21  4992.1 1965.74  4999.6 1965.16  5000.1 1964.66
  5006.6 1964.66  5007.1 1965.16  5034.4 1967.22  5048.5 1972.31  5076.8 1979.06
  5088.0 1982.66  5105.1 1987.58  5119.2 1989.17  5144.0 1992.86  5147.5 1992.86
#Mann=4,-1,0
  4782.5     0.1       0  4999.6    0.05       0  5007.1     0.1       0
  5088.0    0.07       0
Bank Sta=4999.6,5007.1
Exp/Cntr=0.3,0.1

Type RM Length L Ch R = 1,27816,451,451,451
BEGIN DESCRIPTION:
Fall Branch 56.0
END DESCRIPTION:
XS GIS Cut Line= 3
      1879175.00     13971475.02      1879175.00     13971625.00
      1879175.00     13971925.02
#Sta/Elev= 30
  4849.7 2007.14  4869.7 2005.14  4879.7 2003.52  4886.7 2001.56  4909.7 1993.29
  4919.7 1988.89  4949.7 1969.71  4959.7 1965.38  4975.9 1964.04  4976.4 1963.54
  4982.9 1963.54  4983.4 1964.04  4989.7 1964.89  5002.2 1964.75  5019.7 1965.96
  5029.7 1964.76  5039.7 1964.61  5069.7 1966.61  5079.7 1968.40  5083.4 1969.58
  5089.7 1971.60  5099.7 1972.13  5119.7 1975.72  5169.7 1977.52  5181.7 1978.83
  5219.7 1983.29  5239.7 1984.87  5259.7 1987.66  5280.1 1989.65  5299.7 1990.53
#Mann=7,-1,0
  4849.7     0.1       0  4886.7    0.07       0  4975.9    0.05       0
  4983.4    0.07       0  5083.4   0.035       0  5181.7     0.1       0
  5280.1    0.07       0
Bank Sta=4975.9,4983.4
Exp/Cntr=0.3,0.1

Type RM Length L Ch R = 1,27365,426,426,426
BEGIN DESCRIPTION:
Fall Branch 55.0
END DESCRIPTION:
XS GIS Cut Line= 3
      1878775.00     13971575.01      1878775.00     13971675.00
      1878775.00     13972025.01
#Sta/Elev= 30
  4900.4 1992.63  4930.4 1989.71  4940.4 1988.15  4950.4 1986.22  4960.4 1982.81
  4970.4 1976.30  4980.4 1965.53  4990.4 1959.21  4994.1 1955.35  4994.6 1954.85
  5001.2 1954.85  5001.7 1955.35  5010.4 1955.45  5020.4 1956.58  5040.4 1957.46
  5060.4 1960.99  5080.4 1962.94  5105.3 1963.88  5140.4 1963.57  5160.4 1964.41
  5190.4 1968.54  5209.2 1972.53  5220.4 1975.11  5250.4 1980.44  5260.4 1982.62
  5280.4 1987.81  5331.5 1993.29  5340.4 1994.38  5347.9 1996.07  5350.4 1996.07
#Mann=6,-1,0
  4900.4    0.07       0  4994.1    0.05       0  5001.7    0.07       0
  5105.3   0.035       0  5209.2    0.07       0  5331.5     0.1       0
Bank Sta=4994.1,5001.7
Exp/Cntr=0.3,0.1

Type RM Length L Ch R = 1,26939,475,475,475
BEGIN DESCRIPTION:
Fall Branch 54.0
END DESCRIPTION:
XS GIS Cut Line= 3
      1878675.01     13971524.99      1878425.00     13971875.00
      1878375.01     13971974.97
#Sta/Elev= 30
  4569.3 1993.24  4582.8 1992.33  4641.8 1984.91  4683.6 1981.03  4704.5 1980.33
  4769.6 1967.43  4798.2 1963.23  4840.9 1960.56  4855.6 1960.59  4891.3 1956.61
  4906.0 1958.17  4919.8 1956.48  4926.9 1956.67  4950.3 1954.41  4962.6 1955.10
  4971.2 1954.61  5002.2 1952.51  5004.0 1951.68  5004.5 1951.18  5011.7 1951.68
  5013.4 1951.73  5021.8 1954.90  5030.2 1959.03  5035.8 1960.72  5044.1 1966.63
  5052.5 1974.08  5058.1 1976.56  5074.9 1989.92  5088.9 1995.64  5111.2 1998.04
#Mann=5,-1,0
  4569.3    0.07       0  4798.2   0.035       0  4919.8    0.07       0
  5004.0    0.05       0  5011.7    0.07       0
Bank Sta=5004,5011.7
Exp/Cntr=0.3,0.1

Type RM Length L Ch R = 1,26464,486,486,486
BEGIN DESCRIPTION:
Fall Branch 53.0
END DESCRIPTION:
XS GIS Cut Line= 3
      1878475.03     13971424.99      1878175.00     13971525.00
      1878075.02     13971674.97
#Sta/Elev= 30
  4678.6 1982.59  4720.8 1979.88  4731.3 1976.84  4763.0 1970.72  4794.6 1965.17
  4807.7 1964.11  4878.9 1956.82  4889.5 1954.88  4921.1 1952.33  4931.6 1952.38
  4942.2 1950.96  4952.7 1945.41  4963.2 1944.18  5004.5 1943.19  5005.0 1942.69
  5012.2 1943.19  5044.4 1944.92  5053.5 1954.77  5059.5 1959.66  5074.5 1963.29
  5080.5 1966.42  5089.5 1968.71  5110.5 1977.40  5125.6 1979.37  5131.6 1978.45
  5146.6 1980.91  5152.6 1980.28  5161.6 1981.41  5167.6 1980.62  5175.1 1982.17
#Mann=4,-1,0
  4678.6   0.035       0  4807.7    0.07       0  5004.5    0.05       0
  5012.2    0.07       0
Bank Sta=5004.5,5012.2
Exp/Cntr=0.3,0.1

Type RM Length L Ch R = 1,25978,476,476,476
BEGIN DESCRIPTION:
Fall Branch 52.0
END DESCRIPTION:
XS GIS Cut Line= 3
      1878425.02     13971075.00      1878175.00     13971075.00
      1877975.02     13971075.00
#Sta/Elev= 30
  4750.8 1983.05  4780.8 1980.52  4800.8 1974.31  4820.8 1968.97  4889.8 1956.26
  4900.8 1953.96  4920.8 1945.35  4930.8 1942.77  4950.8 1941.00  4980.8 1940.53
  4990.8 1939.70  4998.3 1938.23  5003.3 1938.23  5010.8 1933.83  5015.6 1933.49
  5016.5 1933.43  5017.0 1932.93  5024.7 1932.93  5025.2 1933.43  5030.8 1938.54
  5060.8 1940.48  5070.8 1943.30  5080.8 1948.31  5090.8 1951.62  5110.8 1960.86
  5130.8 1968.72  5150.8 1977.58  5160.8 1980.87  5170.8 1982.65  5200.8 1985.80
#Mann=5,-1,0
  4750.8     0.1       0  4889.8    0.07       0  5015.6     0.1       0
  5016.5    0.05       0  5025.2     0.1       0
Bank Sta=5016.5,5025.2
Exp/Cntr=0.3,0.1

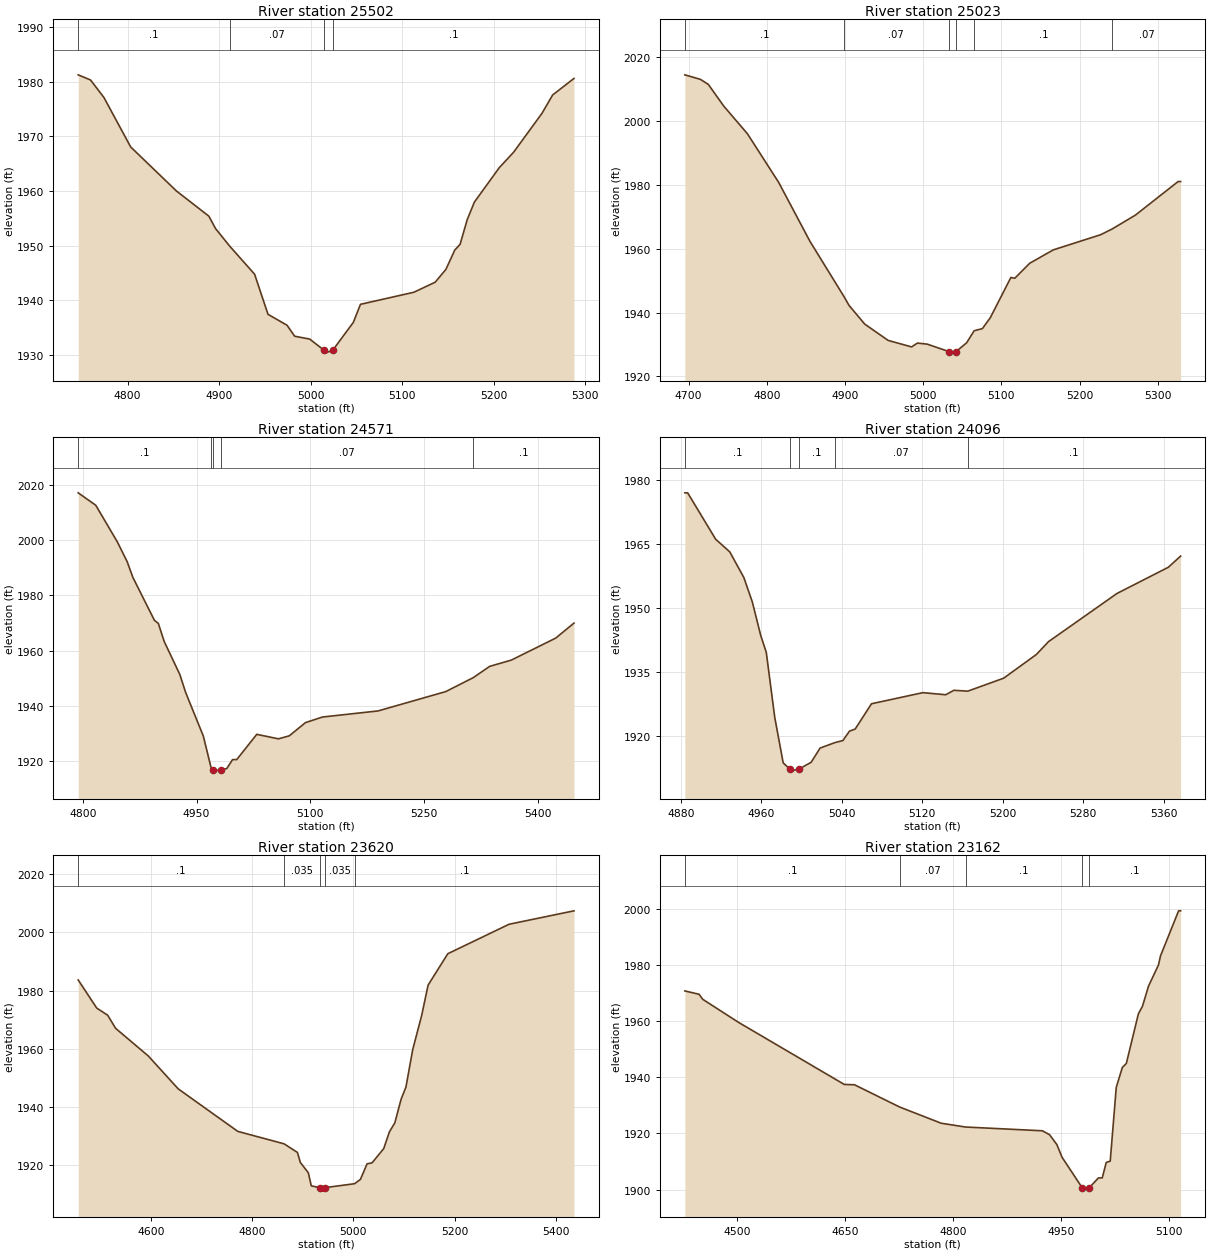
Type RM Length L Ch R = 1,25502,479,479,479
BEGIN DESCRIPTION:
Fall Branch 51.0
END DESCRIPTION:
XS GIS Cut Line= 3
      1878474.99     13970824.99      1878275.00     13970675.00
      1878025.03     13970525.02
#Sta/Elev= 30
  4746.1 1981.27  4759.6 1980.32  4774.2 1977.12  4803.4 1968.06  4853.4 1959.99
  4888.8 1955.38  4896.1 1953.11  4911.5 1949.90  4938.8 1944.74  4953.4 1937.40
  4974.2 1935.40  4982.5 1933.39  4999.0 1932.86  5014.8 1930.79  5015.3 1930.29
  5024.0 1930.79  5046.6 1935.92  5054.4 1939.23  5112.7 1941.44  5136.0 1943.28
  5147.7 1945.63  5157.4 1949.17  5163.2 1950.22  5171.0 1954.75  5178.8 1957.95
  5206.0 1964.26  5221.6 1967.08  5252.7 1974.23  5264.3 1977.58  5287.6 1980.61
#Mann=4,-1,0
  4746.1     0.1       0  4911.5    0.07       0  5014.8    0.05       0
  5024.0     0.1       0
Bank Sta=5014.8,5024
Exp/Cntr=0.3,0.1

Type RM Length L Ch R = 1,25023,452,452,452
BEGIN DESCRIPTION:
Fall Branch 50.0
END DESCRIPTION:
XS GIS Cut Line= 3
      1878674.97     13970225.00      1878375.00     13970225.00
      1878043.58     13970267.47
#Sta/Elev= 30
  4695.1 2014.44  4715.1 2013.01  4725.1 2011.45  4745.1 2004.58  4775.1 1996.00
  4815.1 1980.76  4855.1 1962.30  4898.3 1945.13  4905.1 1942.23  4925.1 1936.39
  4955.1 1931.26  4985.1 1929.23  4992.6 1930.43  5005.2 1930.09  5032.7 1927.78
  5033.2 1927.28  5042.1 1927.78  5055.6 1930.54  5065.1 1934.29  5075.7 1934.96
  5085.8 1938.39  5112.1 1950.97  5117.1 1950.73  5136.2 1955.43  5166.5 1959.63
  5227.0 1964.37  5242.0 1966.21  5271.4 1970.51  5326.0 1981.02  5329.2 1981.02
#Mann=6,-1,0
  4695.1     0.1       0  4898.3    0.07       0  5032.7    0.05       0
  5042.1    0.07       0  5065.1     0.1       0  5242.0    0.07       0
Bank Sta=5032.7,5042.1
Exp/Cntr=0.3,0.1

Type RM Length L Ch R = 1,24571,475,475,475
BEGIN DESCRIPTION:
Fall Branch 49.0
END DESCRIPTION:
XS GIS Cut Line= 3
      1878575.04     13969724.99      1878375.00     13969775.00
      1877989.28     13970002.30
#Sta/Elev= 30
  4793.9 2017.14  4817.1 2012.63  4845.5 1999.37  4858.4 1992.25  4866.1 1986.44
  4894.4 1970.96  4899.6 1969.81  4907.3 1963.29  4927.9 1951.35  4935.7 1944.74
  4958.9 1929.04  4969.0 1917.74  4972.2 1916.80  4972.7 1916.30  4981.6 1916.80
  4989.8 1917.22  4997.5 1920.48  5003.0 1920.48  5029.4 1929.63  5058.1 1928.00
  5072.3 1929.09  5093.7 1933.89  5116.2 1935.91  5189.4 1938.11  5278.7 1945.12
  5314.8 1950.15  5336.7 1954.27  5365.1 1956.52  5423.7 1964.50  5447.8 1969.94
#Mann=5,-1,0
  4793.9     0.1       0  4969.0    0.07       0  4972.2    0.05       0
  4981.6    0.07       0  5314.8     0.1       0
Bank Sta=4972.2,4981.6
Exp/Cntr=0.3,0.1

Type RM Length L Ch R = 1,24096,476,476,476
BEGIN DESCRIPTION:
Fall Branch 48.0
END DESCRIPTION:
XS GIS Cut Line= 3
      1878124.99     13969375.02      1878075.00     13969475.00
      1877894.50     13969810.78
#Sta/Elev= 30
  4884.0 1977.08  4886.8 1977.08  4914.7 1966.16  4928.7 1963.20  4942.7 1957.16
  4951.1 1951.44  4959.4 1943.61  4965.0 1939.58  4973.4 1924.31  4981.8 1913.62
  4988.3 1912.18  4988.8 1911.68  4997.7 1912.18  5009.6 1913.76  5018.5 1917.10
  5033.2 1918.38  5041.2 1918.87  5047.7 1921.08  5053.4 1921.57  5069.6 1927.51
  5120.7 1930.12  5143.4 1929.63  5151.6 1930.68  5165.3 1930.47  5201.1 1933.53
  5233.6 1939.10  5245.6 1942.10  5313.7 1953.43  5364.8 1959.59  5377.0 1962.22
#Mann=5,-1,0
  4884.0     0.1       0  4988.3    0.05       0  4997.7     0.1       0
  5033.2    0.07       0  5165.3     0.1       0
Bank Sta=4988.3,4997.7
Exp/Cntr=0.3,0.1

Type RM Length L Ch R = 1,23620,458,458,458
BEGIN DESCRIPTION:
Fall Branch 47.0
END DESCRIPTION:
XS GIS Cut Line= 3
      1878101.42     13969101.58      1877625.00     13969375.00
      1877232.10     13969552.40
#Sta/Elev= 30
  4455.8 1983.65  4492.4 1974.00  4514.0 1971.55  4529.8 1967.04  4594.5 1957.53
  4653.5 1946.26  4771.4 1931.65  4862.9 1927.38  4889.3 1924.42  4895.1 1920.98
  4910.9 1917.43  4916.7 1912.96  4933.3 1912.32  4933.8 1911.82  4943.2 1912.32
  5002.3 1913.68  5013.9 1915.16  5027.0 1920.50  5037.0 1920.86  5060.0 1925.75
  5071.1 1931.44  5081.9 1934.58  5094.3 1942.68  5103.9 1946.87  5117.4 1959.81
  5135.0 1971.46  5147.7 1981.87  5186.7 1992.66  5307.8 2002.78  5436.2 2007.39
#Mann=5,-1,0
  4455.8     0.1       0  4862.9   0.035       0  4933.3   0.035       0
  4943.2   0.035       0  5002.3     0.1       0
Bank Sta=4933.3,4943.2
Exp/Cntr=0.3,0.1

Type RM Length L Ch R = 1,23162,467,467,467
BEGIN DESCRIPTION:
Fall Branch 46.0
END DESCRIPTION:
XS GIS Cut Line= 3
      1878049.76     13969031.94      1877475.00     13968975.00
      1877374.98     13968924.99
#Sta/Elev= 30
  4426.8 1970.73  4446.6 1969.54  4451.7 1967.75  4501.9 1959.47  4648.5 1937.44
  4662.7 1937.32  4725.5 1929.40  4783.3 1923.63  4817.1 1922.28  4924.0 1920.94
  4934.0 1919.54  4944.1 1916.03  4951.4 1911.48  4979.3 1900.67  4979.8 1900.17
  4989.2 1900.67  5001.9 1904.16  5007.2 1904.16  5012.8 1909.68  5018.3 1910.13
  5026.7 1936.40  5035.1 1943.45  5040.7 1944.91  5057.5 1962.60  5063.1 1965.23
  5071.5 1972.41  5085.4 1979.97  5088.2 1983.20  5113.4 1999.25  5116.2 1999.25
#Mann=5,-1,0
  4426.8     0.1       0  4725.5    0.07       0  4817.1     0.1       0
  4979.3    0.05       0  4989.2     0.1       0
Bank Sta=4979.3,4989.2
Exp/Cntr=0.3,0.1

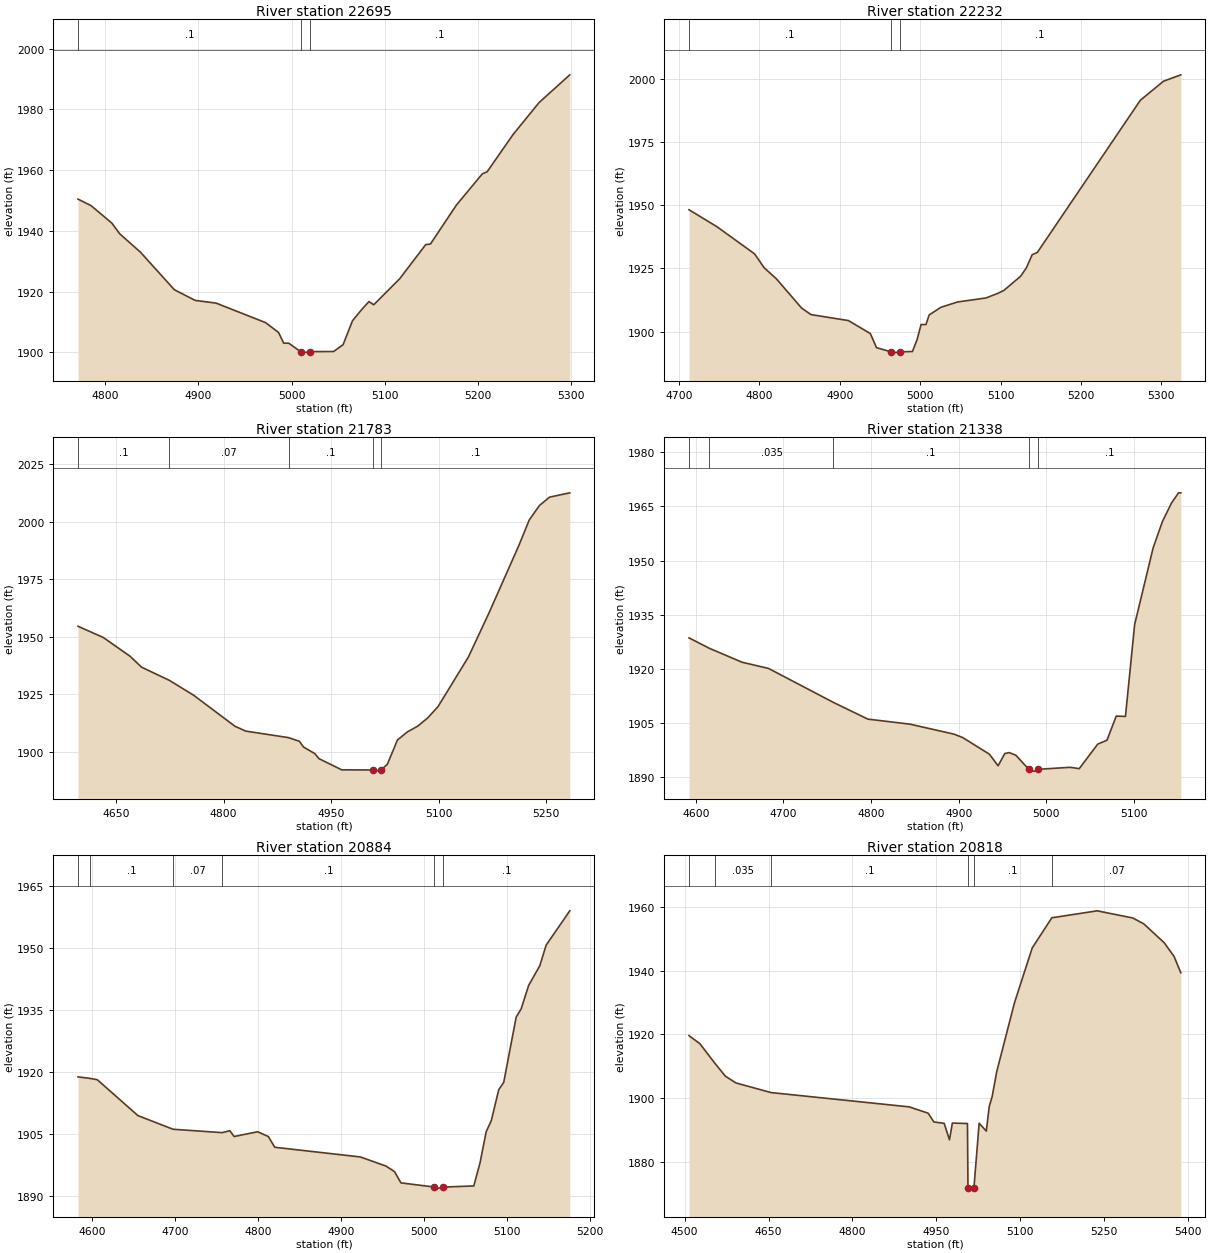
Type RM Length L Ch R = 1,22695,463,463,463
BEGIN DESCRIPTION:
Fall Branch 45.0
END DESCRIPTION:
XS GIS Cut Line= 3
      1877875.02     13968675.01      1877675.00     13968575.00
      1877374.97     13968625.01
#Sta/Elev= 30
  4770.8 1950.48  4784.8 1948.34  4807.2 1942.56  4815.5 1939.08  4837.9 1932.98
  4874.2 1920.64  4896.6 1917.12  4919.0 1916.23  4972.1 1909.81  4986.0 1906.58
  4991.6 1903.03  4997.0 1903.03  5009.7 1900.26  5010.2 1899.76  5019.7 1900.26
  5045.1 1900.29  5055.3 1902.54  5065.4 1910.43  5075.5 1914.19  5083.1 1916.75
  5088.2 1915.68  5116.1 1924.27  5144.0 1935.51  5149.0 1935.67  5176.9 1948.52
  5204.8 1958.82  5209.9 1959.48  5237.7 1971.73  5265.6 1982.26  5298.6 1991.41
#Mann=3,-1,0
  4770.8     0.1       0  5009.7    0.05       0  5019.7     0.1       0
Bank Sta=5009.7,5019.7
Exp/Cntr=0.3,0.1

Type RM Length L Ch R = 1,22232,449,449,449
BEGIN DESCRIPTION:
Fall Branch 44.0
END DESCRIPTION:
XS GIS Cut Line= 3
      1878075.00     13968325.00      1877825.00     13968175.00
      1877575.00     13967975.00
#Sta/Elev= 30
  4712.5 1948.20  4747.5 1941.43  4794.1 1930.76  4805.8 1925.34  4821.3 1920.86
  4852.4 1909.41  4864.1 1906.80  4910.7 1904.44  4938.0 1899.30  4945.7 1893.74
  4963.8 1892.08  4964.3 1891.58  4974.3 1892.08  4990.4 1892.23  4996.3 1897.07
  5001.1 1902.87  5007.2 1902.87  5011.2 1906.67  5025.7 1909.67  5046.5 1911.78
  5081.7 1913.35  5096.1 1915.11  5104.1 1916.35  5124.9 1921.92  5132.1 1925.26
  5139.3 1930.44  5145.7 1931.33  5273.8 1991.41  5302.6 1998.94  5324.2 2001.47
#Mann=3,-1,0
  4712.5     0.1       0  4963.8    0.05       0  4974.3     0.1       0
Bank Sta=4963.8,4974.3
Exp/Cntr=0.3,0.1

Type RM Length L Ch R = 1,21783,445,445,445
BEGIN DESCRIPTION:
Fall Branch 43.0
END DESCRIPTION:
XS GIS Cut Line= 3
      1878274.98     13968174.96      1878075.00     13967825.00
      1877875.01     13967625.01
#Sta/Elev= 30
  4596.9 1954.62  4632.1 1949.74  4669.6 1941.55  4685.4 1936.84  4724.3 1931.09
  4758.1 1924.63  4815.7 1911.15  4830.8 1909.02  4890.6 1906.17  4905.7 1904.58
  4911.4 1902.10  4927.3 1899.21  4933.0 1897.03  4964.7 1892.17  5008.9 1892.11
  5009.4 1891.61  5019.4 1892.11  5028.3 1894.56  5042.4 1905.13  5056.5 1908.72
  5070.7 1911.16  5084.8 1914.79  5099.0 1919.66  5141.4 1941.25  5169.7 1960.11
  5212.1 1989.97  5226.2 2000.81  5240.4 2007.10  5254.5 2010.76  5282.8 2012.64
#Mann=5,-1,0
  4596.9     0.1       0  4724.3    0.07       0  4890.6     0.1       0
  5008.9    0.05       0  5019.4     0.1       0
Bank Sta=5008.9,5019.4
Exp/Cntr=0.3,0.1

Type RM Length L Ch R = 1,21338,454,454,454
BEGIN DESCRIPTION:
Fall Branch 42.0
END DESCRIPTION:
XS GIS Cut Line= 3
      1878475.00     13967975.02      1878425.00     13967575.00
      1878375.01     13967425.04
#Sta/Elev= 30
  4592.3 1928.53  4615.6 1925.62  4652.8 1921.77  4683.0 1920.05  4757.1 1910.61
  4796.4 1905.98  4844.3 1904.59  4894.7 1901.81  4904.7 1900.85  4935.0 1896.26
  4945.0 1893.03  4952.6 1896.43  4957.6 1896.69  4965.2 1895.97  4980.1 1892.05
  4980.6 1891.55  4990.2 1891.55  4990.7 1892.05  5027.1 1892.61  5037.6 1892.24
  5058.7 1899.05  5069.2 1900.12  5079.8 1906.82  5090.3 1906.73  5100.8 1932.23
  5121.9 1953.50  5132.5 1960.82  5143.0 1966.01  5150.9 1968.78  5153.5 1968.78
#Mann=5,-1,0
  4592.3    0.07       0  4615.6   0.035       0  4757.1     0.1       0
  4980.1    0.05       0  4990.7     0.1       0
Bank Sta=4980.1,4990.7
Exp/Cntr=0.3,0.1

Type RM Length L Ch R = 1,20884,66,66,66
BEGIN DESCRIPTION:
Fall Branch 41.0
END DESCRIPTION:
XS GIS Cut Line= 3
      1878725.00     13967875.02      1878825.00     13967475.00
      1878725.00     13967325.00
#Sta/Elev= 30
  4583.4 1918.84  4597.3 1918.49  4606.6 1918.16  4655.6 1909.46  4697.9 1906.15
  4757.1 1905.33  4766.4 1905.79  4771.5 1904.39  4799.9 1905.54  4812.8 1904.38
  4820.5 1901.78  4923.6 1899.44  4954.5 1897.23  4964.8 1895.89  4972.5 1893.16
  5012.9 1892.14  5013.4 1891.64  5023.6 1892.14  5060.3 1892.41  5067.8 1897.97
  5075.3 1905.57  5081.4 1908.20  5090.4 1915.75  5096.4 1917.51  5111.4 1933.33
  5117.4 1935.31  5126.4 1940.98  5139.9 1945.80  5147.5 1950.76  5176.0 1959.08
#Mann=6,-1,0
  4583.4   0.035       0  4597.3     0.1       0  4697.9    0.07       0
  4757.1     0.1       0  5012.9    0.05       0  5023.6     0.1       0
Bank Sta=5012.9,5023.6
Exp/Cntr=0.3,0.1

Type RM Length L Ch R = 1,20818,204,204,204
BEGIN DESCRIPTION:
Fall Branch 41.1
END DESCRIPTION:
XS GIS Cut Line= 4
      1878784.31     13967906.00      1878892.82     13967494.73
      1878862.44     13967392.73      1878749.79     13967063.44
#Sta/Elev= 30
  4507.8 1919.61  4527.2 1917.09  4553.6 1911.05  4572.7 1906.93  4591.6 1904.79
  4654.4 1901.77  4901.8 1897.28  4935.6 1895.30  4945.8 1892.56  4964.2 1892.13
  4973.7 1886.97  4978.9 1892.21  5005.9 1892.06  5006.8 1872.00  5007.3 1871.50
  5017.5 1872.00  5026.8 1892.16  5039.6 1889.69  5044.8 1897.33  5050.1 1900.55
  5058.3 1908.36  5090.0 1929.91  5121.7 1947.08  5156.8 1956.56  5238.0 1958.74
  5301.4 1956.51  5321.2 1954.68  5357.8 1948.75  5375.4 1944.48  5387.6 1939.32
#Mann=6,-1,0
  4507.8    0.07       0  4553.6   0.035       0  4654.4     0.1       0
  5006.8    0.05       0  5017.5     0.1       0  5156.8    0.07       0
Bank Sta=5006.8,5017.5
Exp/Cntr=0.3,0.1