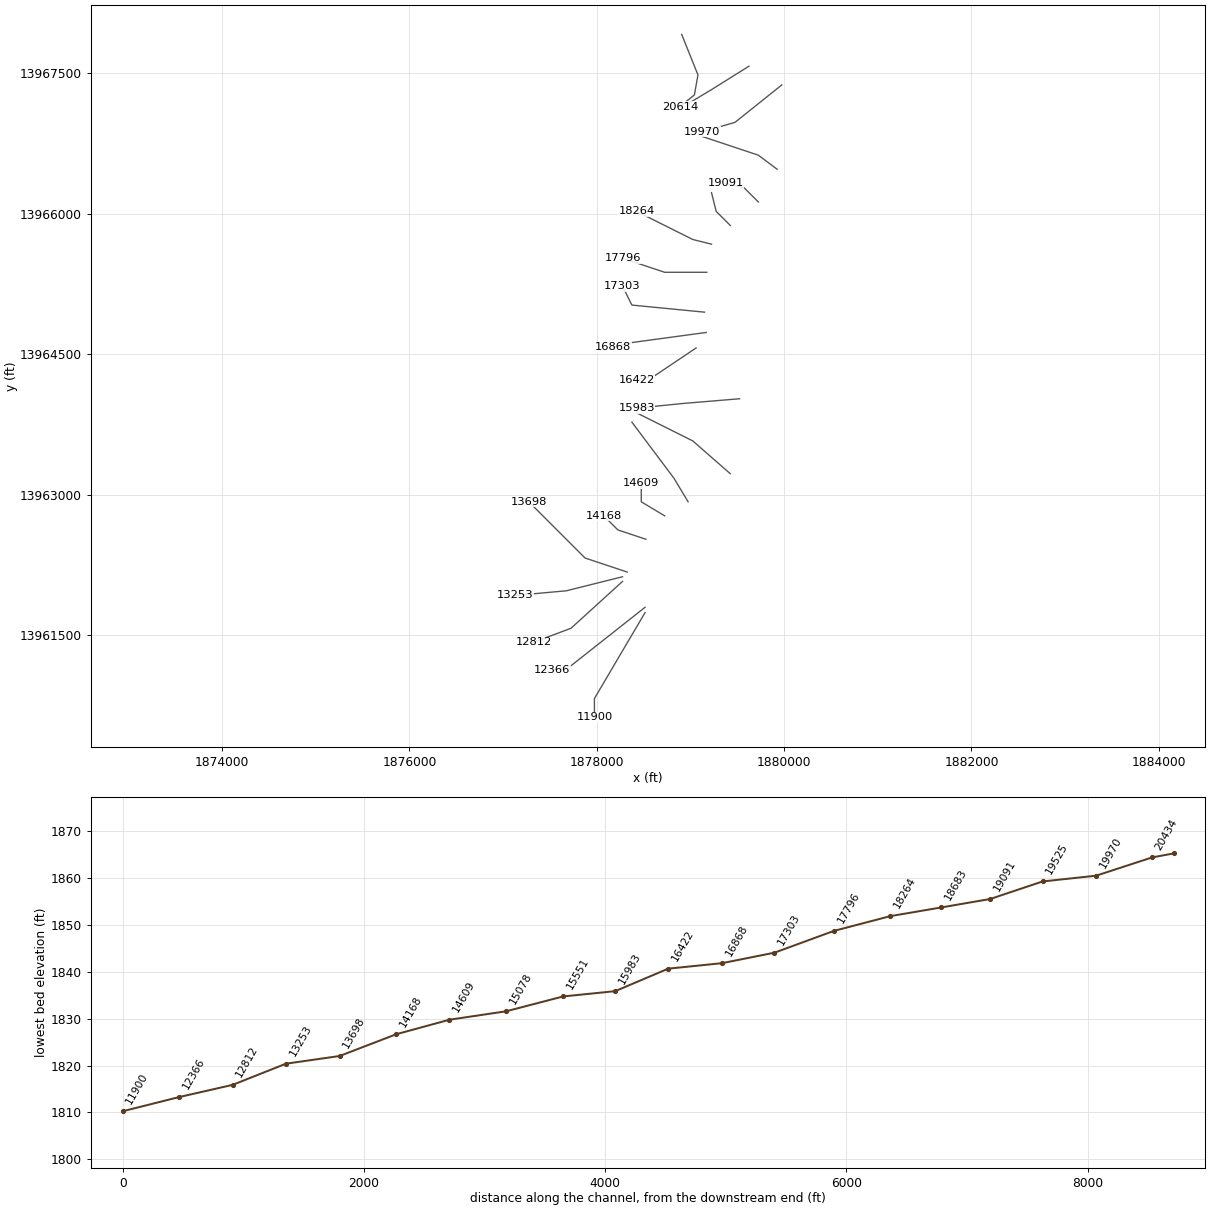
HEC-RAS study Fall Branch.prj: Fall Branch Base Level Engineering

--- Fall Branch.g01 (geometry) --- (continued)

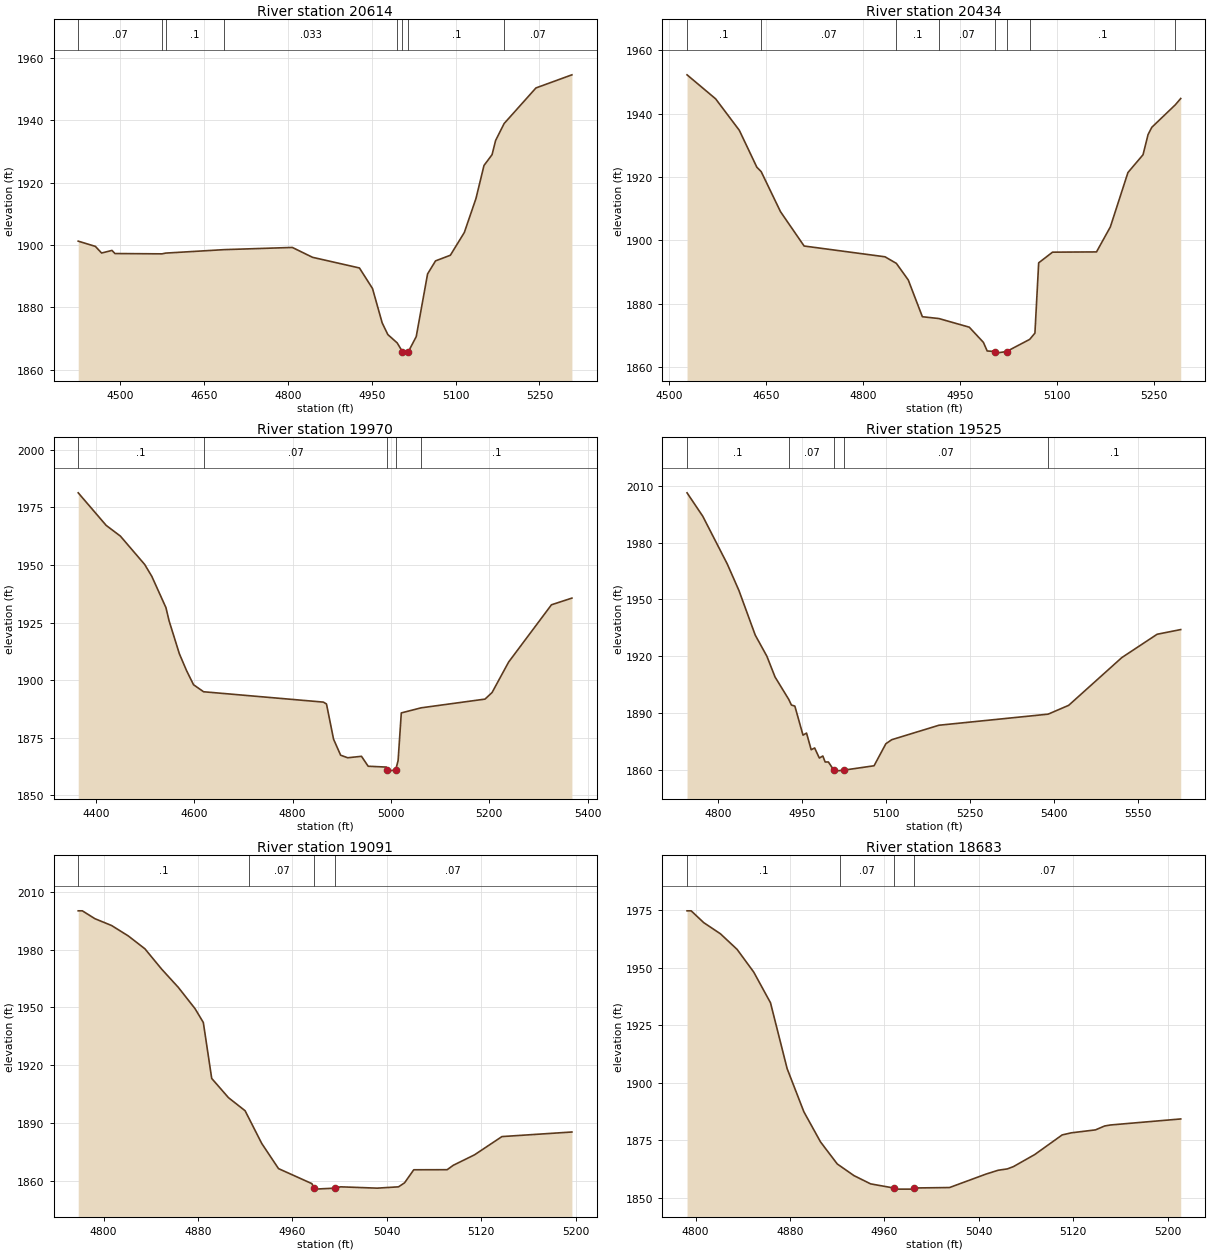
Type RM Length L Ch R = 1,20614,180,180,180
BEGIN DESCRIPTION:
Fall Branch 41.2
END DESCRIPTION:
XS GIS Cut Line= 4
      1878906.66     13967913.79      1879080.29     13967481.47
      1879042.09     13967267.93      1878885.85     13967142.94
#Sta/Elev= 30
  4425.1 1901.23  4455.8 1899.54  4466.9 1897.42  4485.4 1898.25  4490.8 1897.25
  4575.1 1897.15  4581.4 1897.39  4686.0 1898.50  4808.0 1899.21  4844.1 1896.04
  4928.0 1892.62  4951.4 1886.02  4968.7 1874.98  4978.8 1871.23  4995.5 1868.56
  5004.9 1865.77  5005.4 1865.27  5015.6 1865.77  5029.6 1870.57  5049.9 1890.71
  5064.1 1894.89  5090.6 1896.70  5115.6 1904.01  5136.4 1914.91  5150.8 1925.54
  5165.2 1929.00  5171.6 1933.58  5186.8 1939.00  5243.7 1950.43  5308.0 1954.64
#Mann=8,-1,0
  4425.1    0.07       0  4575.1   0.033       0  4581.4     0.1       0
  4686.0   0.033       0  4995.5     0.1       0  5004.9    0.05       0
  5015.6     0.1       0  5186.8    0.07       0
Bank Sta=5004.9,5015.6
Exp/Cntr=0.3,0.1

Type RM Length L Ch R = 1,20434,464,464,464
BEGIN DESCRIPTION:
Fall Branch 40.0
END DESCRIPTION:
XS GIS Cut Line= 3
      1879625.00     13967575.00      1879225.00     13967325.00
      1878975.04     13967175.02
#Sta/Elev= 30
  4528.3 1952.27  4572.5 1944.69  4609.1 1934.76  4636.2 1923.11  4642.9 1921.72
  4672.8 1909.06  4709.3 1898.23  4834.3 1894.83  4851.9 1892.75  4870.3 1887.51
  4892.1 1875.91  4917.6 1875.34  4964.6 1872.61  4986.4 1867.83  4992.3 1865.10
  5005.0 1864.92  5005.5 1864.42  5022.2 1864.92  5058.0 1868.76  5066.1 1870.73
  5071.9 1892.92  5093.3 1896.29  5161.3 1896.37  5182.7 1904.27  5209.9 1921.43
  5233.2 1927.04  5241.0 1933.42  5246.8 1935.71  5283.1 1942.80  5291.5 1944.80
#Mann=8,-1,0
  4528.3     0.1       0  4642.9    0.07       0  4851.9     0.1       0
  4917.6    0.07       0  5005.0    0.05       0  5022.2    0.07       0
  5058.0     0.1       0  5283.1    0.07       0
Bank Sta=5005,5022.2
Exp/Cntr=0.3,0.1

Type RM Length L Ch R = 1,19970,445,445,445
BEGIN DESCRIPTION:
Fall Branch 39.0
END DESCRIPTION:
XS GIS Cut Line= 3
      1879975.04     13967375.03      1879475.00     13966975.00
      1879124.97     13966874.99
#Sta/Elev= 30
  4363.8 1981.28  4420.7 1967.14  4449.5 1962.52  4499.1 1950.17  4513.5 1945.04
  4542.3 1931.45  4548.7 1925.71  4569.5 1911.49  4584.0 1904.23  4598.4 1898.01
  4618.9 1894.96  4862.5 1890.47  4868.9 1889.65  4883.3 1874.37  4897.7 1867.43
  4912.1 1866.32  4940.1 1866.95  4953.7 1862.64  4990.6 1862.28  4992.4 1861.02
  4992.9 1860.52  5009.6 1861.02  5014.6 1865.09  5021.1 1885.78  5061.5 1887.99
  5191.4 1891.77  5205.7 1894.61  5239.5 1907.86  5326.6 1932.70  5368.2 1935.60
#Mann=5,-1,0
  4363.8     0.1       0  4618.9    0.07       0  4992.4    0.05       0
  5009.6    0.07       0  5061.5     0.1       0
Bank Sta=4992.4,5009.6
Exp/Cntr=0.3,0.1

Type RM Length L Ch R = 1,19525,434,434,434
BEGIN DESCRIPTION:
Fall Branch 38.0
END DESCRIPTION:
XS GIS Cut Line= 3
      1879925.01     13966474.99      1879725.00     13966625.00
      1879124.97     13966825.01
#Sta/Elev= 30
  4744.6 2006.35  4772.7 1993.98  4816.5 1968.75  4837.3 1954.78  4866.5 1931.17
  4887.3 1920.01  4901.9 1909.03  4926.5 1897.14  4931.1 1894.23  4937.3 1893.65
  4951.9 1878.29  4958.2 1879.39  4966.5 1870.59  4972.7 1871.51  4981.1 1866.19
  4987.3 1867.28  4991.5 1864.11  4997.3 1864.11  5007.0 1859.78  5007.5 1859.28
  5024.4 1859.78  5078.9 1862.11  5100.0 1873.75  5110.6 1875.90  5194.9 1883.53
  5390.0 1889.38  5426.8 1894.05  5521.7 1919.26  5584.9 1931.61  5627.1 1934.09
#Mann=5,-1,0
  4744.6     0.1       0  4926.5    0.07       0  5007.0    0.05       0
  5024.4    0.07       0  5390.0     0.1       0
Bank Sta=5007,5024.4
Exp/Cntr=0.3,0.1

Type RM Length L Ch R = 1,19091,408,408,408
BEGIN DESCRIPTION:
Fall Branch 37.0
END DESCRIPTION:
XS GIS Cut Line= 3
      1879724.98     13966125.02      1879575.00     13966275.00
      1879374.96     13966325.01
#Sta/Elev= 30
  4778.5 2000.09  4782.0 2000.09  4792.6 1996.02  4806.8 1992.45  4820.9 1987.06
  4835.0 1980.37  4849.2 1969.80  4863.3 1960.34  4877.5 1949.26  4884.5 1942.09
  4891.6 1913.04  4905.8 1903.05  4919.9 1896.25  4923.5 1891.91  4934.0 1879.25
  4948.2 1866.20  4976.5 1858.39  4978.3 1856.04  4978.8 1855.54  4995.8 1856.04
  5000.9 1856.73  5031.8 1856.05  5049.9 1856.73  5055.0 1858.81  5062.8 1865.59
  5091.1 1865.63  5096.3 1867.93  5114.3 1873.36  5137.5 1882.83  5196.8 1885.21
#Mann=4,-1,0
  4778.5     0.1       0  4923.5    0.07       0  4978.3    0.05       0
  4995.8    0.07       0
Bank Sta=4978.3,4995.8
Exp/Cntr=0.3,0.1

Type RM Length L Ch R = 1,18683,419,419,419
BEGIN DESCRIPTION:
Fall Branch 36.0
END DESCRIPTION:
XS GIS Cut Line= 3
      1879424.99     13965875.01      1879275.00     13966025.00
      1879224.99     13966225.03
#Sta/Elev= 30
  4792.7 1974.77  4796.2 1974.77  4806.8 1969.65  4821.0 1964.77  4835.1 1958.01
  4849.2 1948.13  4863.4 1934.79  4877.5 1906.15  4891.7 1887.35  4905.8 1874.26
  4920.0 1864.66  4922.1 1863.91  4934.1 1859.62  4948.2 1856.02  4967.7 1854.23
  4968.2 1853.73  4984.8 1853.73  4985.3 1854.23  5015.1 1854.42  5046.0 1860.27
  5056.3 1861.94  5064.1 1862.53  5069.2 1863.51  5087.3 1868.77  5110.5 1877.29
  5118.2 1878.21  5138.8 1879.50  5146.5 1881.19  5151.7 1881.64  5211.0 1884.25
#Mann=4,-1,0
  4792.7     0.1       0  4922.1    0.07       0  4967.7    0.05       0
  4985.3    0.07       0
Bank Sta=4967.7,4985.3
Exp/Cntr=0.3,0.1

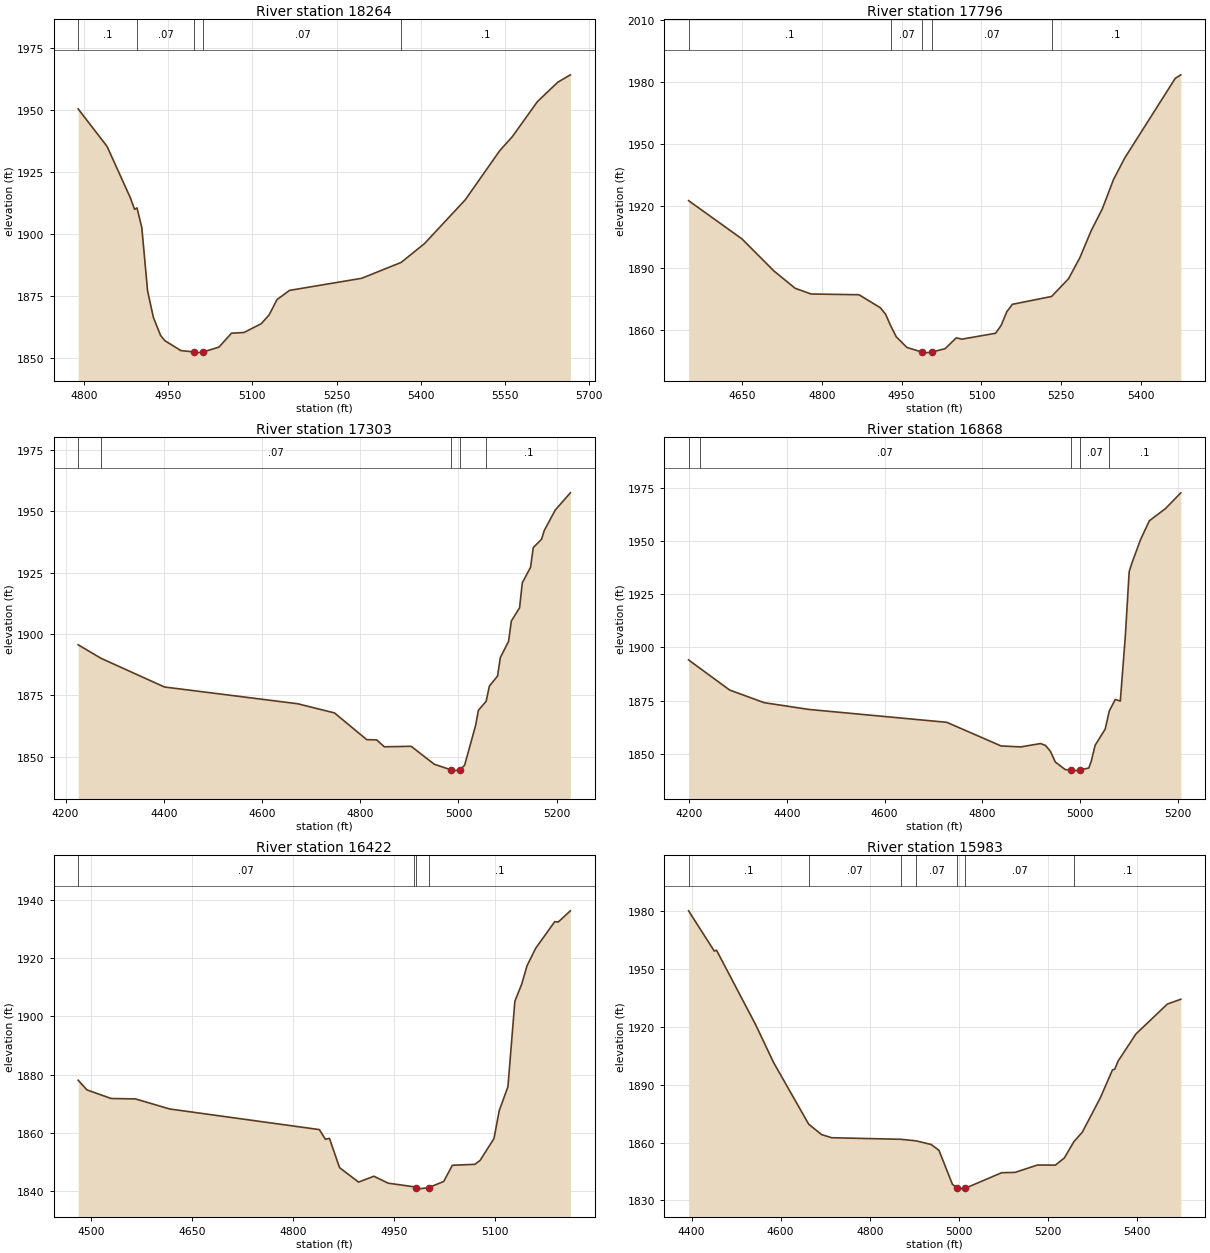
Type RM Length L Ch R = 1,18264,468,468,468
BEGIN DESCRIPTION:
Fall Branch 35.0
END DESCRIPTION:
XS GIS Cut Line= 3
      1879224.99     13965675.00      1879025.00     13965725.00
      1878424.97     13966025.01
#Sta/Elev= 30
  4789.5 1950.43  4841.0 1935.30  4882.3 1914.68  4890.0 1909.92  4894.4 1910.47
  4902.9 1902.58  4913.2 1877.02  4923.5 1866.34  4936.4 1859.00  4944.1 1856.91
  4972.5 1852.92  4995.2 1852.39  4995.7 1851.89  5012.8 1852.39  5040.4 1854.32
  5062.7 1859.92  5085.1 1860.22  5115.8 1863.78  5129.8 1867.32  5143.8 1873.49
  5166.1 1877.20  5294.7 1882.08  5365.1 1888.50  5406.5 1896.06  5479.2 1913.74
  5540.7 1933.58  5563.1 1939.23  5607.8 1953.37  5644.1 1961.19  5666.5 1964.17
#Mann=5,-1,0
  4789.5     0.1       0  4894.4    0.07       0  4995.2    0.05       0
  5012.8    0.07       0  5365.1     0.1       0
Bank Sta=4995.2,5012.8
Exp/Cntr=0.3,0.1

Type RM Length L Ch R = 1,17796,493,493,493
BEGIN DESCRIPTION:
Fall Branch 34.0
END DESCRIPTION:
XS GIS Cut Line= 3
      1879175.00     13965375.00      1878725.00     13965375.00
      1878275.04     13965524.99
#Sta/Elev= 30
  4550.0 1922.57  4650.0 1904.09  4710.0 1888.58  4750.0 1880.15  4780.0 1877.37
  4870.0 1877.01  4910.0 1870.73  4920.0 1867.57  4929.3 1862.09  4940.0 1856.65
  4960.0 1851.48  4988.7 1849.24  4989.2 1848.74  5006.4 1849.24  5031.6 1850.88
  5052.7 1856.14  5063.2 1855.51  5126.5 1858.36  5137.0 1862.19  5147.6 1868.80
  5158.1 1872.38  5231.6 1876.17  5263.5 1884.77  5284.6 1894.87  5305.7 1907.84
  5326.8 1918.53  5347.9 1932.76  5368.9 1943.17  5463.8 1981.75  5474.3 1983.48
#Mann=5,-1,0
  4550.0     0.1       0  4929.3    0.07       0  4988.7    0.05       0
  5006.4    0.07       0  5231.6     0.1       0
Bank Sta=4988.7,5006.4
Exp/Cntr=0.3,0.1

Type RM Length L Ch R = 1,17303,435,435,435
BEGIN DESCRIPTION:
Fall Branch 33.0
END DESCRIPTION:
XS GIS Cut Line= 3
      1879149.78     13964949.33      1878375.00     13965025.00
      1878274.99     13965225.03
#Sta/Elev= 30
  4225.7 1895.60  4272.1 1890.10  4401.3 1878.39  4672.6 1871.56  4747.5 1867.83
  4813.3 1856.92  4833.4 1856.83  4849.1 1854.01  4903.7 1854.21  4950.8 1846.89
  4985.1 1844.59  4985.6 1844.09  5003.1 1844.59  5012.5 1846.50  5034.9 1862.72
  5040.5 1868.86  5056.4 1872.60  5062.9 1878.75  5079.6 1882.87  5085.2 1890.38
  5102.0 1896.99  5107.6 1905.27  5124.4 1910.67  5129.9 1920.83  5146.7 1927.18
  5152.3 1935.23  5169.1 1938.59  5174.7 1942.19  5197.0 1950.52  5227.8 1957.54
#Mann=5,-1,0
  4225.7     0.1       0  4272.1    0.07       0  4985.1    0.05       0
  5003.1    0.07       0  5056.4     0.1       0
Bank Sta=4985.1,5003.1
Exp/Cntr=0.3,0.1

Type RM Length L Ch R = 1,16868,446,446,446
BEGIN DESCRIPTION:
Fall Branch 32.0
END DESCRIPTION:
XS GIS Cut Line= 3
      1879168.21     13964732.65      1878375.00     13964625.00
      1878175.04     13964575.01
#Sta/Elev= 30
  4199.2 1894.11  4222.4 1890.19  4283.2 1879.96  4353.8 1874.01  4445.8 1870.83
  4727.2 1864.79  4838.2 1853.69  4878.6 1853.23  4918.9 1854.81  4929.0 1853.94
  4939.1 1851.19  4949.2 1846.13  4969.4 1842.58  4980.5 1842.35  4981.0 1841.85
  4998.7 1842.35  5017.7 1843.32  5022.9 1846.71  5030.6 1854.00  5051.2 1861.61
  5059.6 1870.18  5071.8 1875.52  5082.1 1874.77  5092.5 1905.81  5100.2 1935.55
  5105.3 1939.29  5123.4 1950.62  5141.4 1959.46  5174.9 1965.32  5205.8 1972.63
#Mann=5,-1,0
  4199.2     0.1       0  4222.4    0.07       0  4980.5    0.05       0
  4998.7    0.07       0  5059.6     0.1       0
Bank Sta=4980.5,4998.7
Exp/Cntr=0.3,0.1

Type RM Length L Ch R = 1,16422,439,439,439
BEGIN DESCRIPTION:
Fall Branch 31.0
END DESCRIPTION:
XS GIS Cut Line= 3
      1879060.67     13964567.36      1878625.00     13964275.00
      1878425.03     13964225.01
#Sta/Elev= 30
  4480.6 1878.08  4493.6 1874.75  4529.6 1871.80  4565.7 1871.65  4616.7 1868.19
  4838.7 1861.12  4847.7 1857.80  4853.7 1858.12  4868.7 1848.06  4896.9 1843.10
  4919.7 1845.10  4940.8 1842.73  4978.9 1841.49  4982.7 1841.18  4983.2 1840.68
  5000.9 1841.18  5023.3 1843.30  5036.2 1848.87  5069.7 1849.20  5077.4 1850.55
  5098.0 1858.05  5105.8 1867.64  5118.7 1875.84  5129.0 1905.17  5139.3 1911.15
  5147.0 1917.34  5159.9 1923.38  5188.2 1932.51  5193.4 1932.39  5211.4 1936.23
#Mann=4,-1,0
  4480.6    0.07       0  4978.9     0.1       0  4982.7    0.05       0
  5000.9     0.1       0
Bank Sta=4982.7,5000.9
Exp/Cntr=0.3,0.1

Type RM Length L Ch R = 1,15983,432,432,432
BEGIN DESCRIPTION:
Fall Branch 30.0
END DESCRIPTION:
XS GIS Cut Line= 3
      1879524.99     13964025.00      1878925.00     13963975.00
      1878424.96     13963925.00
#Sta/Elev= 30
  4393.4 1979.90  4451.1 1959.08  4456.1 1959.52  4543.9 1920.96  4584.0 1901.46
  4662.9 1869.51  4691.9 1864.10  4714.5 1862.48  4869.7 1861.67  4903.9 1860.87
  4937.8 1858.97  4955.3 1855.95  4985.4 1838.41  4996.4 1836.38  4996.9 1835.88
  5014.7 1836.38  5096.0 1844.37  5126.1 1844.54  5176.4 1848.36  5216.6 1848.30
  5236.7 1852.02  5258.1 1860.46  5276.9 1865.34  5317.1 1882.98  5344.7 1897.62
  5349.7 1897.91  5357.3 1902.16  5397.5 1916.23  5467.8 1931.65  5498.0 1934.14
#Mann=7,-1,0
  4393.4     0.1       0  4662.9    0.07       0  4869.7     0.1       0
  4903.9    0.07       0  4996.4    0.05       0  5014.7    0.07       0
  5258.1     0.1       0
Bank Sta=4996.4,5014.7
Exp/Cntr=0.3,0.1

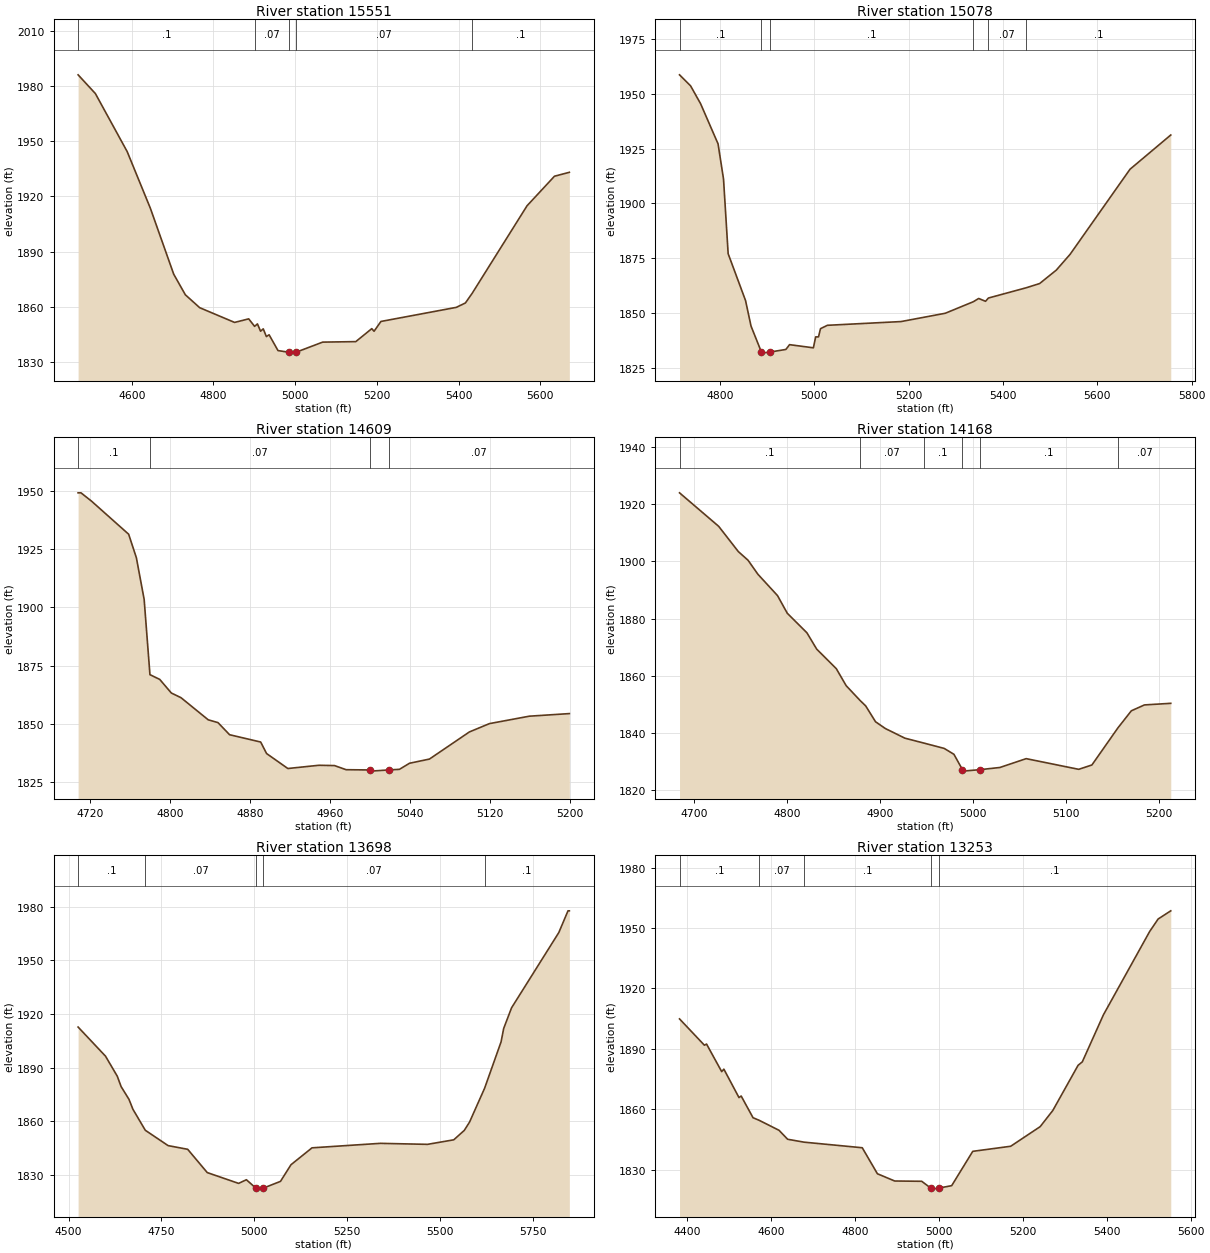
Type RM Length L Ch R = 1,15551,473,473,473
BEGIN DESCRIPTION:
Fall Branch 29.0
END DESCRIPTION:
XS GIS Cut Line= 3
      1879425.02     13963224.98      1879025.00     13963575.00
      1878424.96     13963875.02
#Sta/Elev= 30
  4468.6 1986.20  4510.9 1976.00  4588.7 1944.44  4645.6 1913.52  4702.6 1877.72
  4731.1 1866.50  4766.2 1859.48  4851.6 1851.46  4886.2 1853.40  4900.6 1849.32
  4907.6 1850.65  4915.2 1846.67  4921.8 1847.96  4929.4 1843.77  4936.1 1844.73
  4957.9 1836.13  4983.9 1835.25  4984.4 1834.75  5002.2 1835.25  5067.2 1840.74
  5148.3 1841.01  5187.4 1848.07  5193.0 1846.65  5209.8 1851.98  5394.2 1859.65
  5416.6 1862.05  5433.0 1867.25  5567.5 1914.95  5634.6 1931.02  5671.0 1933.15
#Mann=5,-1,0
  4468.6     0.1       0  4900.6    0.07       0  4983.9    0.05       0
  5002.2    0.07       0  5433.0     0.1       0
Bank Sta=4983.9,5002.2
Exp/Cntr=0.3,0.1

Type RM Length L Ch R = 1,15078,469,469,469
BEGIN DESCRIPTION:
Fall Branch 28.0
END DESCRIPTION:
XS GIS Cut Line= 3
      1878975.02     13962924.96      1878825.00     13963175.00
      1878375.00     13963775.01
#Sta/Elev= 30
  4714.1 1958.83  4737.5 1953.80  4758.8 1945.62  4795.8 1927.27  4807.4 1911.16
  4817.2 1877.05  4854.1 1855.61  4865.7 1843.96  4887.7 1832.08  4888.2 1831.58
  4906.0 1832.08  4939.6 1833.26  4947.4 1835.45  4997.9 1834.01  5002.8 1839.01
  5008.8 1839.01  5013.0 1842.76  5027.6 1844.30  5183.8 1846.01  5277.6 1849.81
  5337.2 1855.10  5348.4 1856.57  5363.0 1855.28  5369.0 1856.77  5448.6 1861.43
  5477.6 1863.39  5513.0 1869.54  5542.2 1876.75  5669.2 1915.64  5755.7 1931.32
#Mann=6,-1,0
  4714.1     0.1       0  4887.7    0.05       0  4906.0     0.1       0
  5337.2   0.035       0  5369.0    0.07       0  5448.6     0.1       0
Bank Sta=4887.7,4906
Exp/Cntr=0.3,0.1

Type RM Length L Ch R = 1,14609,441,441,441
BEGIN DESCRIPTION:
Fall Branch 27.0
END DESCRIPTION:
XS GIS Cut Line= 3
      1878725.02     13962774.99      1878475.00     13962925.00
      1878475.00     13963125.03
#Sta/Elev= 30
  4708.1 1949.13  4711.0 1949.13  4721.7 1945.50  4758.7 1931.37  4766.4 1921.32
  4774.2 1903.45  4779.8 1872.27  4780.0 1871.16  4789.8 1869.12  4801.4 1863.29
  4811.1 1861.28  4838.3 1851.80  4848.1 1850.59  4859.7 1845.40  4890.8 1842.27
  4896.7 1837.34  4918.0 1830.91  4949.1 1832.30  4964.7 1832.17  4976.3 1830.40
  5000.5 1830.29  5001.0 1829.79  5018.8 1830.29  5029.7 1830.56  5039.7 1833.16
  5059.7 1834.96  5099.7 1846.60  5119.7 1850.16  5159.7 1853.35  5199.7 1854.46
#Mann=4,-1,0
  4708.1     0.1       0  4779.8    0.07       0  5000.5    0.05       0
  5018.8    0.07       0
Bank Sta=5000.5,5018.8
Exp/Cntr=0.3,0.1

Type RM Length L Ch R = 1,14168,470,470,470
BEGIN DESCRIPTION:
Fall Branch 26.0
END DESCRIPTION:
XS GIS Cut Line= 3
      1878524.96     13962525.01      1878225.00     13962625.00
      1878075.01     13962774.99
#Sta/Elev= 30
  4684.1 1923.92  4726.2 1912.22  4747.3 1903.41  4757.8 1900.36  4768.4 1895.47
  4789.5 1888.01  4800.0 1881.84  4821.1 1875.02  4831.6 1869.33  4852.7 1862.49
  4863.3 1856.55  4878.3 1851.37  4884.3 1849.48  4894.9 1843.94  4905.4 1841.58
  4926.5 1838.20  4946.9 1836.49  4968.7 1834.63  4979.2 1832.57  4988.4 1827.19
  4988.9 1826.69  5006.8 1827.19  5028.6 1827.96  5056.9 1831.05  5113.4 1827.32
  5127.6 1828.84  5155.5 1841.77  5170.0 1847.77  5184.1 1849.82  5212.4 1850.38
#Mann=6,-1,0
  4684.1     0.1       0  4878.3    0.07       0  4946.9     0.1       0
  4988.4    0.05       0  5006.8     0.1       0  5155.5    0.07       0
Bank Sta=4988.4,5006.8
Exp/Cntr=0.3,0.1

Type RM Length L Ch R = 1,13698,445,445,445
BEGIN DESCRIPTION:
Fall Branch 25.0
END DESCRIPTION:
XS GIS Cut Line= 3
      1878324.98     13962175.01      1877875.00     13962325.00
      1877274.97     13962925.03
#Sta/Elev= 30
  4525.7 1912.64  4599.5 1896.37  4631.1 1885.21  4641.6 1879.33  4662.7 1872.24
  4673.3 1866.69  4706.7 1854.94  4768.1 1846.36  4820.8 1844.31  4873.5 1831.29
  4957.9 1825.25  4978.9 1827.29  5004.8 1822.54  5005.3 1822.04  5023.6 1822.54
  5070.7 1826.37  5099.0 1835.68  5155.6 1845.12  5339.4 1847.63  5466.7 1847.07
  5537.4 1849.61  5565.7 1854.88  5579.9 1859.54  5620.4 1878.43  5664.7 1904.33
  5671.8 1911.87  5693.0 1923.40  5820.3 1965.49  5845.0 1977.61  5848.6 1977.61
#Mann=5,-1,0
  4525.7     0.1       0  4706.7    0.07       0  5004.8    0.05       0
  5023.6    0.07       0  5620.4     0.1       0
Bank Sta=5004.8,5023.6
Exp/Cntr=0.3,0.1

Type RM Length L Ch R = 1,13253,441,441,441
BEGIN DESCRIPTION:
Fall Branch 24.0
END DESCRIPTION:
XS GIS Cut Line= 3
      1878275.00     13962125.00      1877675.00     13961975.00
      1877125.03     13961925.00
#Sta/Elev= 30
  4381.5 1904.87  4440.8 1891.82  4445.9 1892.39  4482.0 1878.70  4487.2 1879.94
  4523.2 1865.83  4528.4 1866.60  4556.7 1855.84  4571.7 1854.51  4618.6 1849.60
  4639.2 1845.14  4678.2 1843.71  4817.0 1840.93  4853.1 1828.03  4894.3 1824.43
  4958.7 1824.29  4980.3 1820.90  4980.8 1820.40  4999.1 1820.90  5030.1 1822.12
  5080.3 1839.15  5170.7 1841.67  5241.0 1851.41  5271.1 1859.43  5331.3 1881.83
  5341.4 1883.56  5391.6 1906.86  5502.0 1948.28  5522.1 1954.44  5552.2 1958.50
#Mann=5,-1,0
  4381.5     0.1       0  4571.7    0.07       0  4678.2     0.1       0
  4980.3    0.05       0  4999.1     0.1       0
Bank Sta=4980.3,4999.1
Exp/Cntr=0.3,0.1

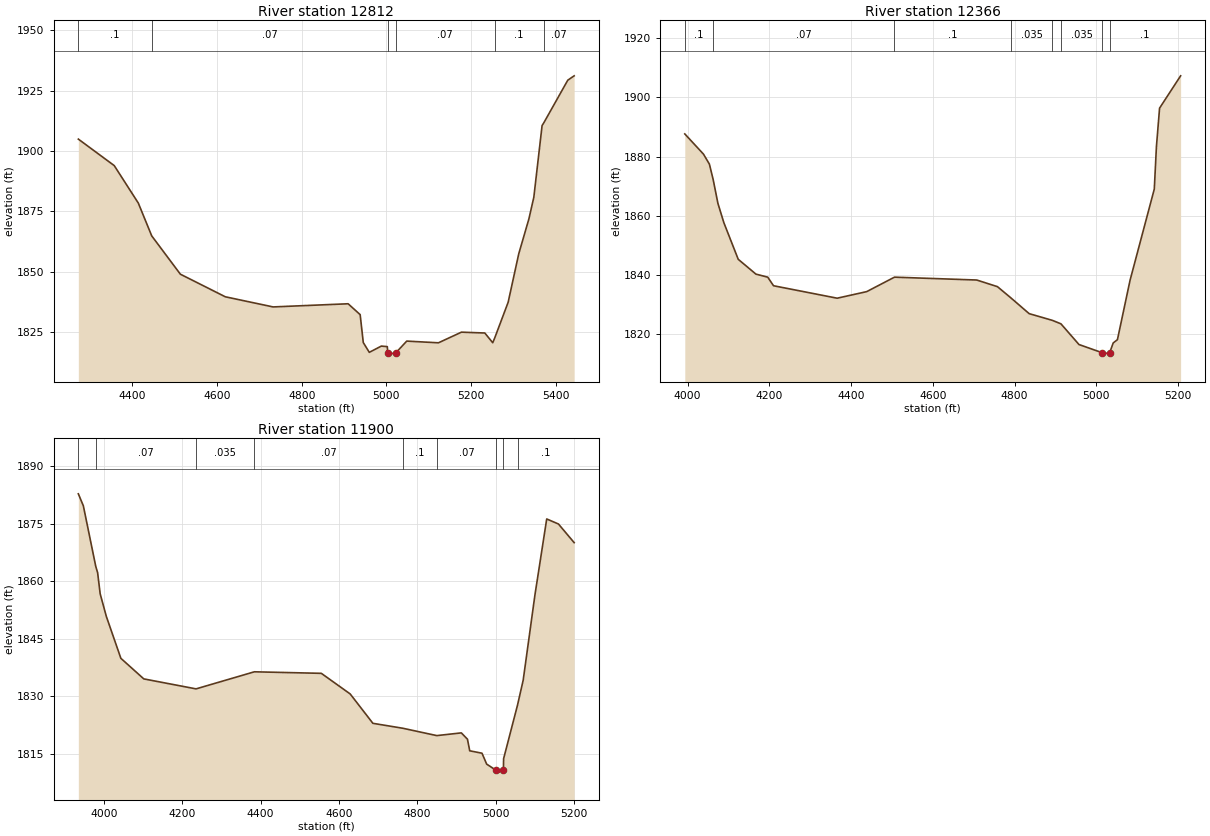
Type RM Length L Ch R = 1,12812,446,446,446
BEGIN DESCRIPTION:
Fall Branch 23.0
END DESCRIPTION:
XS GIS Cut Line= 3
      1878275.00     13962075.00      1877725.00     13961575.00
      1877325.00     13961425.00
#Sta/Elev= 30
  4272.7 1904.96  4357.5 1893.98  4414.3 1878.46  4446.0 1864.86  4513.6 1849.00
  4619.7 1839.64  4732.5 1835.44  4909.6 1836.75  4938.0 1832.25  4945.4 1820.68
  4959.6 1816.63  4988.0 1819.22  5002.1 1818.99  5003.2 1816.39  5003.7 1815.89
  5022.0 1816.39  5048.0 1821.29  5122.8 1820.58  5177.1 1824.99  5232.3 1824.64
  5251.0 1820.61  5255.9 1822.69  5287.4 1837.39  5312.4 1857.45  5336.4 1871.93
  5348.0 1880.88  5367.5 1910.59  5371.2 1911.60  5428.1 1929.35  5443.2 1931.17
#Mann=6,-1,0
  4272.7     0.1       0  4446.0    0.07       0  5003.2    0.05       0
  5022.0    0.07       0  5255.9     0.1       0  5371.2    0.07       0
Bank Sta=5003.2,5022
Exp/Cntr=0.3,0.1

Type RM Length L Ch R = 1,12366,466,466,466
BEGIN DESCRIPTION:
Fall Branch 22.0
END DESCRIPTION:
XS GIS Cut Line= 3
      1878515.40     13961798.77      1877725.00     13961175.00
      1877525.05     13961125.01
#Sta/Elev= 30
  3993.1 1887.69  4038.9 1880.84  4053.3 1877.48  4062.6 1872.22  4074.1 1864.23
  4088.6 1857.71  4123.8 1845.32  4167.1 1840.31  4196.0 1839.28  4210.2 1836.38
  4365.9 1832.17  4438.1 1834.39  4506.1 1839.28  4707.4 1838.31  4758.0 1836.07
  4790.8 1832.28  4835.6 1826.95  4892.6 1824.67  4913.3 1823.51  4957.5 1816.51
  5013.8 1813.77  5014.3 1813.27  5032.6 1813.77  5041.2 1817.06  5051.5 1818.15
  5082.5 1838.29  5141.7 1869.05  5146.9 1883.39  5154.6 1896.40  5206.1 1907.32
#Mann=8,-1,0
  3993.1     0.1       0  4062.6    0.07       0  4506.1     0.1       0
  4790.8   0.035       0  4892.6    0.07       0  4913.3   0.035       0
  5013.8   0.035       0  5032.6     0.1       0
Bank Sta=5013.8,5032.6
Exp/Cntr=0.3,0.1

Type RM Length L Ch R = 1,11900,467,467,467
BEGIN DESCRIPTION:
Fall Branch 21.0
END DESCRIPTION:
XS GIS Cut Line= 3
      1878515.68     13961742.43      1877975.00     13960825.00
      1877975.00     13960625.00
#Sta/Elev= 30
  3934.8 1882.80  3947.6 1879.68  3979.3 1863.87  3984.0 1862.27  3990.5 1856.75
  4006.2 1850.86  4043.3 1839.93  4101.8 1834.56  4235.1 1831.96  4383.9 1836.41
  4554.7 1836.01  4628.3 1830.64  4686.3 1822.98  4762.4 1821.70  4849.3 1819.78
  4911.9 1820.49  4927.5 1818.84  4933.3 1815.82  4964.6 1815.19  4976.5 1812.35
  5000.2 1810.76  5000.7 1810.26  5019.2 1810.76  5019.7 1813.75  5055.2 1827.72
  5069.7 1834.24  5099.7 1856.48  5129.7 1876.25  5159.7 1874.93  5199.7 1870.08
#Mann=9,-1,0
  3934.8     0.1       0  3979.3    0.07       0  4235.1   0.035       0
  4383.9    0.07       0  4762.4     0.1       0  4849.3    0.07       0
  5000.2    0.05       0  5019.2    0.07       0  5055.2     0.1       0
Bank Sta=5000.2,5019.2
Exp/Cntr=0.3,0.1