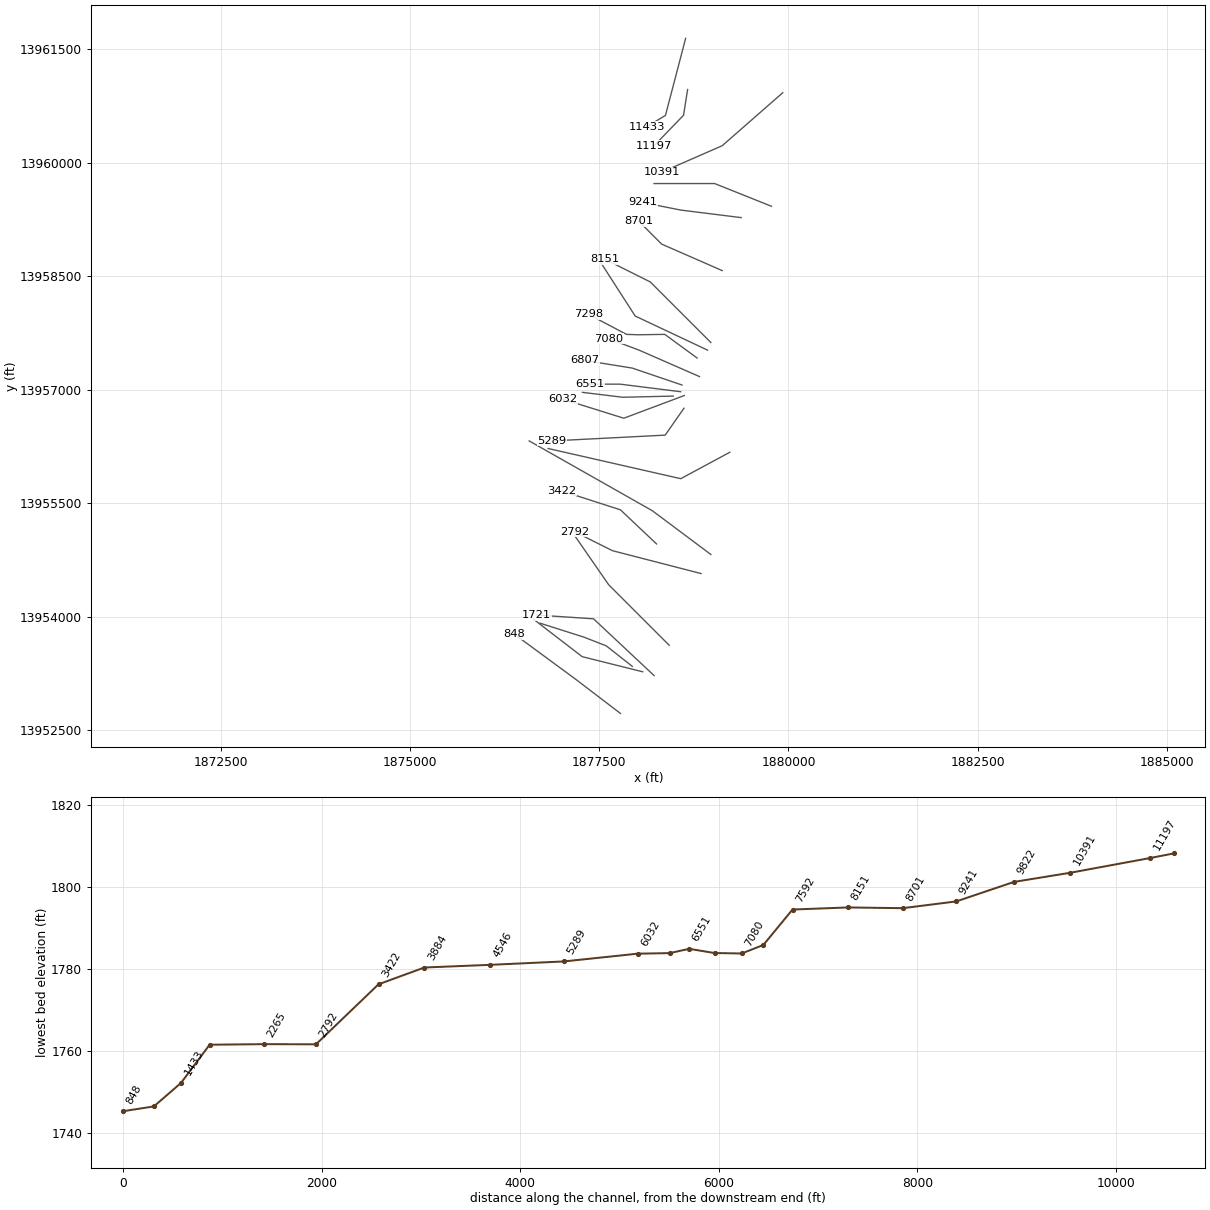
HEC-RAS study Fall Branch.prj: Fall Branch Base Level Engineering

--- Fall Branch.g01 (geometry) --- (continued)

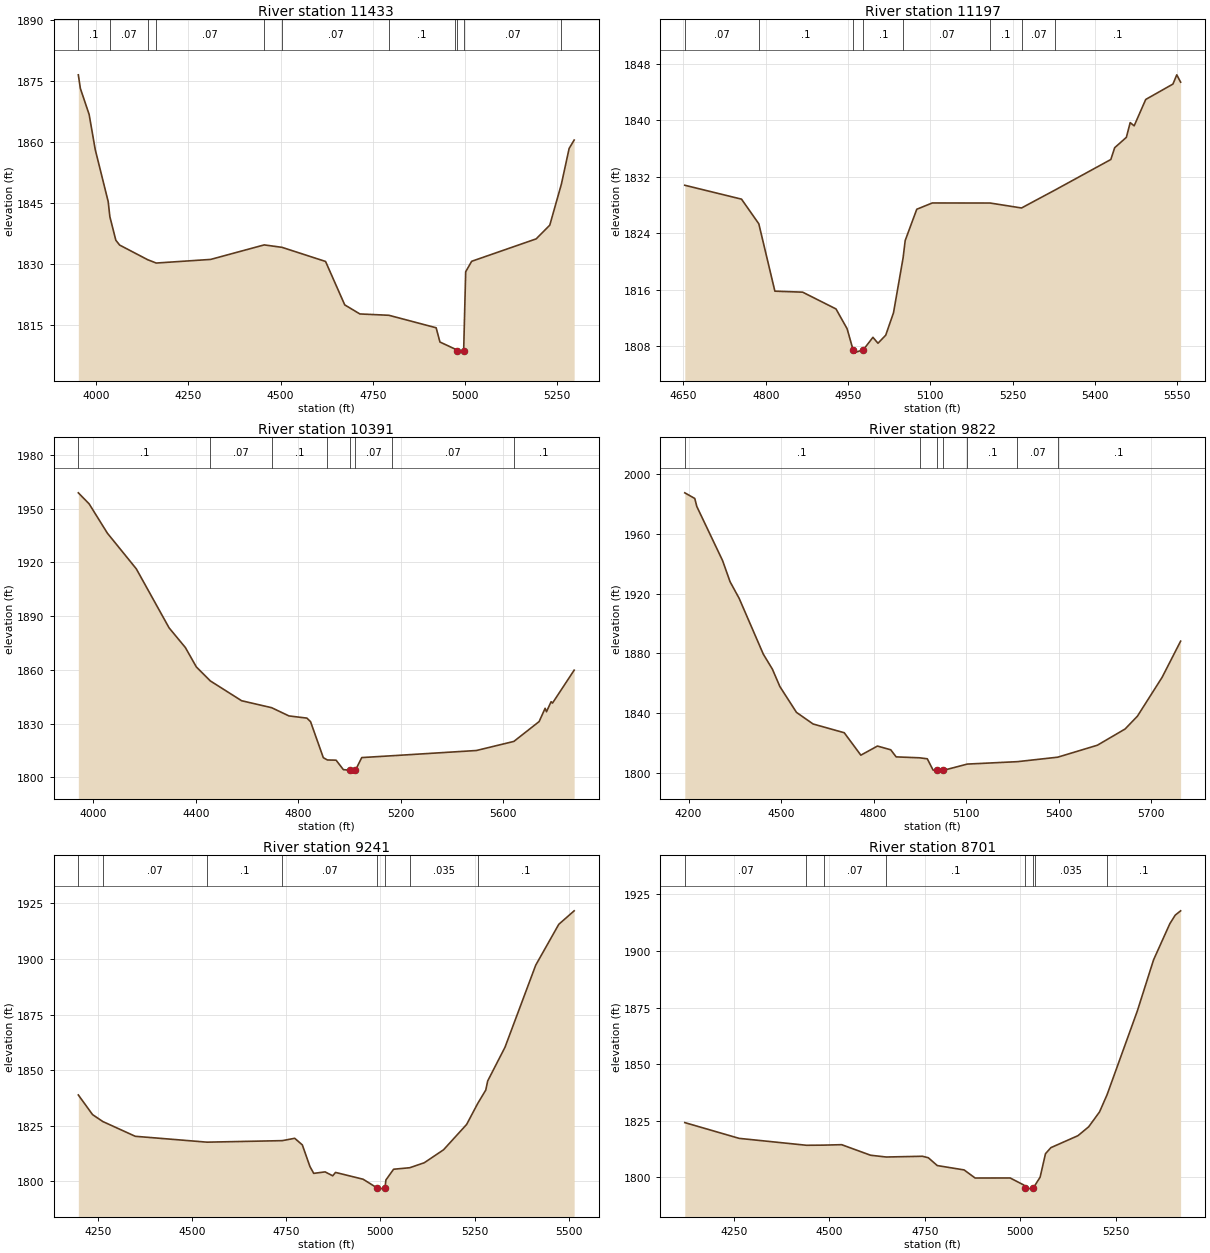
Type RM Length L Ch R = 1,11433,236,236,236
BEGIN DESCRIPTION:
Fall Branch 20.0
END DESCRIPTION:
XS GIS Cut Line= 3
      1878641.90     13961643.38      1878375.00     13960625.00
      1878125.02     13960475.01
#Sta/Elev= 30
  3951.4 1876.54  3956.9 1873.20  3980.7 1866.80  3997.3 1858.14  4032.4 1845.38
  4036.9 1841.67  4053.1 1835.88  4063.4 1834.70  4139.4 1831.10  4162.6 1830.28
  4310.1 1831.17  4455.4 1834.74  4503.6 1834.14  4621.7 1830.67  4673.7 1820.00
  4714.7 1817.77  4793.5 1817.44  4921.5 1814.37  4931.8 1810.87  4971.4 1809.20
  4977.1 1808.64  4977.6 1808.14  4996.1 1808.64  5001.6 1828.14  5017.8 1830.71
  5192.7 1836.22  5229.6 1839.59  5261.2 1849.72  5282.1 1858.45  5295.7 1860.51
#Mann=11,-1,0
  3951.4     0.1       0  4036.9    0.07       0  4139.4   0.035       0
  4162.6    0.07       0  4455.4   0.035       0  4503.6    0.07       0
  4793.5     0.1       0  4971.4    0.07       0  4977.1    0.05       0
  4996.1    0.07       0  5261.2     0.1       0
Bank Sta=4977.1,4996.1
Exp/Cntr=0.3,0.1

Type RM Length L Ch R = 1,11197,806,806,806
BEGIN DESCRIPTION:
Fall Branch 19.0
END DESCRIPTION:
XS GIS Cut Line= 3
      1878667.68     13960967.18      1878613.89     13960627.01
      1878225.02     13960225.02
#Sta/Elev= 30
  4652.4 1830.82  4755.8 1828.85  4787.3 1825.36  4816.6 1815.81  4867.2 1815.67
  4928.0 1813.29  4948.2 1810.49  4959.0 1807.53  4959.5 1807.03  4978.0 1807.53
  4995.3 1809.27  5004.5 1808.43  5018.6 1809.57  5032.8 1812.75  5050.3 1820.54
  5054.1 1822.99  5075.2 1827.42  5103.5 1828.31  5209.0 1828.30  5266.1 1827.60
  5327.6 1830.16  5428.9 1834.47  5435.9 1836.14  5457.2 1837.61  5464.2 1839.70
  5471.4 1839.24  5492.5 1842.98  5542.1 1845.16  5549.1 1846.47  5556.1 1845.43
#Mann=8,-1,0
  4652.4    0.07       0  4787.3     0.1       0  4959.0    0.05       0
  4978.0     0.1       0  5050.3    0.07       0  5209.0     0.1       0
  5266.1    0.07       0  5327.6     0.1       0
Bank Sta=4959,4978
Exp/Cntr=0.3,0.1

Type RM Length L Ch R = 1,10391,569,569,569
BEGIN DESCRIPTION:
Fall Branch 18.0
END DESCRIPTION:
XS GIS Cut Line= 3
      1879924.99     13960924.99      1879125.00     13960225.00
      1878325.01     13959875.01
#Sta/Elev= 30
  3941.5 1958.88  3983.7 1952.72  4054.9 1936.35  4167.9 1916.42  4296.0 1883.44
  4359.6 1872.44  4402.3 1861.64  4457.1 1853.80  4579.3 1842.74  4696.2 1838.87
  4763.9 1834.27  4834.1 1833.04  4848.4 1831.04  4898.2 1810.93  4914.2 1809.66
  4948.0 1809.55  4976.5 1804.26  5003.4 1803.93  5003.9 1803.43  5023.6 1803.93
  5048.2 1811.00  5165.3 1812.01  5496.1 1814.95  5642.2 1820.02  5740.9 1831.10
  5764.3 1838.53  5769.7 1836.61  5787.7 1842.20  5793.1 1841.43  5877.7 1859.82
#Mann=8,-1,0
  3941.5     0.1       0  4457.1    0.07       0  4696.2     0.1       0
  4914.2    0.07       0  5003.4    0.05       0  5023.6    0.07       0
  5165.3    0.07       0  5642.2     0.1       0
Bank Sta=5003.4,5023.6
Exp/Cntr=0.3,0.1

Type RM Length L Ch R = 1,9822,581,581,581
BEGIN DESCRIPTION:
Fall Branch 17.0
END DESCRIPTION:
XS GIS Cut Line= 3
      1879775.02     13959424.99      1879025.00     13959725.00
      1878225.00     13959725.00
#Sta/Elev= 30
  4187.7 1987.35  4220.0 1983.58  4226.8 1978.15  4310.2 1942.03  4334.5 1927.89
  4364.1 1916.70  4442.2 1879.48  4471.8 1869.37  4496.0 1857.76  4549.9 1840.48
  4603.7 1832.72  4704.7 1826.87  4758.6 1811.86  4812.4 1817.96  4855.5 1815.47
  4873.0 1810.72  4949.0 1810.10  4974.0 1809.44  4992.8 1801.89  5005.2 1801.69
  5005.7 1801.19  5025.8 1801.69  5103.7 1805.90  5266.2 1807.52  5397.1 1810.52
  5525.5 1818.51  5615.5 1829.38  5655.5 1837.97  5735.5 1863.95  5795.5 1888.13
#Mann=7,-1,0
  4187.7     0.1       0  4949.0    0.07       0  5005.2    0.05       0
  5025.8    0.07       0  5103.7     0.1       0  5266.2    0.07       0
  5397.1     0.1       0
Bank Sta=5005.2,5025.8
Exp/Cntr=0.3,0.1

Type RM Length L Ch R = 1,9241,540,540,540
BEGIN DESCRIPTION:
Fall Branch 16.0
END DESCRIPTION:
XS GIS Cut Line= 3
      1879374.97     13959275.00      1878575.00     13959375.00
      1878075.00     13959475.00
#Sta/Elev= 30
  4198.3 1838.80  4236.1 1829.96  4263.3 1826.85  4349.4 1820.21  4539.9 1817.57
  4739.5 1818.25  4772.7 1819.31  4792.9 1816.33  4813.0 1806.64  4823.1 1803.53
  4853.3 1804.20  4873.5 1802.43  4881.0 1803.95  4954.1 1800.90  4991.7 1796.94
  4992.2 1796.44  5012.3 1796.94  5014.7 1800.55  5035.1 1805.39  5077.9 1806.06
  5116.7 1808.32  5167.7 1814.14  5228.9 1825.52  5258.5 1835.00  5279.8 1841.01
  5284.9 1845.11  5330.8 1860.26  5412.4 1897.21  5473.6 1915.58  5514.4 1921.65
#Mann=8,-1,0
  4198.3     0.1       0  4263.3    0.07       0  4539.9     0.1       0
  4739.5    0.07       0  4991.7    0.05       0  5012.3    0.07       0
  5077.9   0.035       0  5258.5     0.1       0
Bank Sta=4991.7,5012.3
Exp/Cntr=0.3,0.1

Type RM Length L Ch R = 1,8701,550,550,550
BEGIN DESCRIPTION:
Fall Branch 15.0
END DESCRIPTION:
XS GIS Cut Line= 3
      1879124.98     13958575.01      1878325.00     13958925.00
      1878024.97     13959225.03
#Sta/Elev= 30
  4122.2 1824.19  4264.5 1817.22  4440.6 1814.17  4485.2 1814.23  4532.7 1814.43
  4608.3 1809.77  4649.4 1808.98  4744.3 1809.31  4759.5 1808.65  4782.9 1805.20
  4853.1 1803.28  4882.0 1799.69  4973.6 1799.72  5009.5 1796.59  5013.4 1795.29
  5013.9 1794.79  5034.0 1795.29  5038.3 1796.41  5052.0 1800.06  5066.1 1810.45
  5080.2 1813.12  5151.0 1818.40  5179.2 1822.35  5207.5 1828.91  5227.3 1836.54
  5306.5 1873.56  5348.9 1896.11  5391.4 1912.05  5405.5 1915.85  5419.7 1917.77
#Mann=8,-1,0
  4122.2    0.07       0  4440.6   0.035       0  4485.2    0.07       0
  4649.4     0.1       0  5013.4    0.05       0  5034.0     0.1       0
  5038.3   0.035       0  5227.3     0.1       0
Bank Sta=5013.4,5034
Exp/Cntr=0.3,0.1

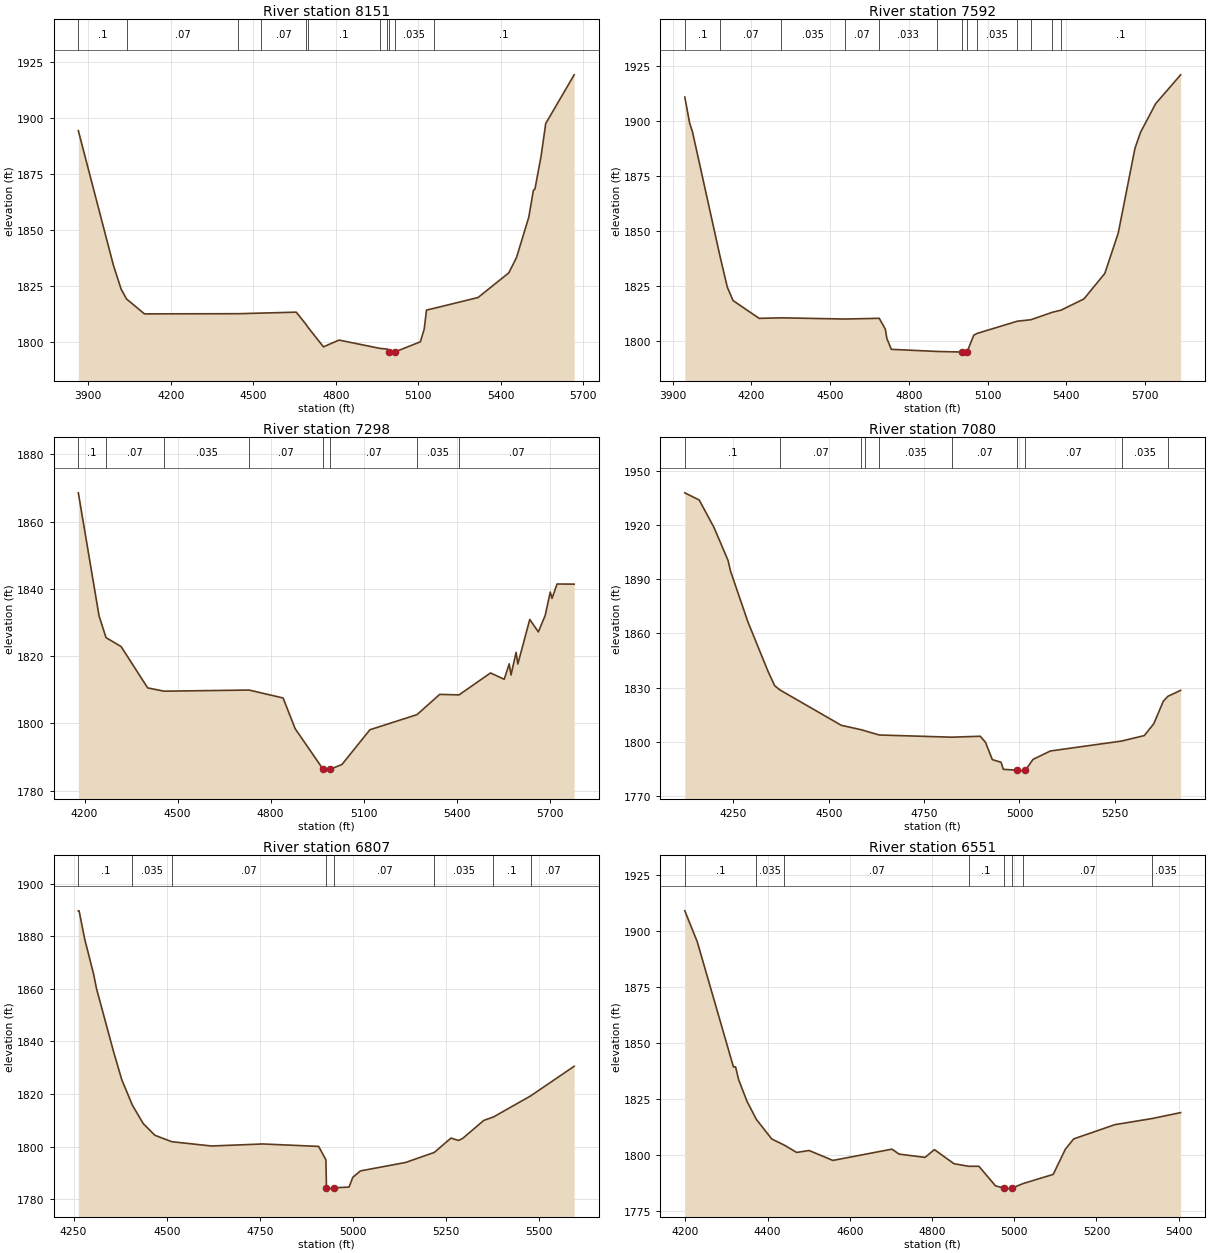
Type RM Length L Ch R = 1,8151,559,559,559
BEGIN DESCRIPTION:
Fall Branch 14.0
END DESCRIPTION:
XS GIS Cut Line= 3
      1878975.00     13957625.00      1878175.00     13958425.00
      1877574.99     13958725.00
#Sta/Elev= 30
  3864.5 1894.26  3991.8 1834.28  4020.1 1823.52  4039.8 1819.13  4104.9 1812.49
  4445.1 1812.56  4527.0 1812.83  4656.5 1813.26  4692.2 1807.79  4699.5 1806.45
  4755.5 1797.77  4812.0 1800.80  4961.7 1797.06  4987.7 1796.79  4993.9 1795.47
  4994.4 1794.97  5014.7 1795.47  5107.7 1800.03  5121.7 1805.69  5130.0 1814.18
  5156.7 1814.95  5317.3 1819.79  5429.1 1830.79  5457.1 1837.62  5501.8 1855.65
  5518.6 1867.68  5524.1 1868.15  5546.5 1882.90  5563.3 1897.43  5666.7 1919.18
#Mann=11,-1,0
  3864.5     0.1       0  4039.8    0.07       0  4445.1   0.035       0
  4527.0    0.07       0  4692.2   0.035       0  4699.5     0.1       0
  4961.7    0.07       0  4987.7   0.035       0  4993.9   0.035       0
  5014.7   0.035       0  5156.7     0.1       0
Bank Sta=4993.9,5014.7
Exp/Cntr=0.3,0.1

Type RM Length L Ch R = 1,7592,294,294,294
BEGIN DESCRIPTION:
Fall Branch 13.0
END DESCRIPTION:
XS GIS Cut Line= 3
      1878931.48     13957524.23      1877975.00     13957975.00
      1877525.03     13958674.96
#Sta/Elev= 30
  3946.4 1910.87  3965.0 1899.00  3975.7 1895.07  4079.9 1838.88  4108.3 1824.50
  4130.4 1818.35  4229.9 1810.26  4314.0 1810.51  4556.2 1809.96  4687.5 1810.29
  4710.7 1805.32  4716.4 1801.13  4733.5 1796.18  4906.8 1795.23  5000.9 1794.96
  5001.4 1794.46  5021.8 1794.96  5047.7 1802.62  5060.3 1803.42  5213.5 1808.97
  5265.7 1809.66  5347.6 1813.06  5380.3 1814.00  5467.4 1819.10  5547.0 1830.70
  5598.2 1849.06  5661.9 1887.58  5683.1 1894.84  5740.8 1907.89  5835.9 1920.99
#Mann=13,-1,0
  3946.4     0.1       0  4079.9    0.07       0  4314.0   0.035       0
  4556.2    0.07       0  4687.5   0.033       0  4906.8    0.07       0
  5000.9    0.05       0  5021.8    0.07       0  5060.3   0.035       0
  5213.5    0.07       0  5265.7     0.1       0  5347.6    0.07       0
  5380.3     0.1       0
Bank Sta=5000.9,5021.8
Exp/Cntr=0.3,0.1

Type RM Length L Ch R = 1,7298,218,218,218
BEGIN DESCRIPTION:
Fall Branch 13.1
END DESCRIPTION:
XS GIS Cut Line= 5
      1878793.45     13957420.06      1878366.35     13957732.58
      1878014.78     13957727.37      1877861.14     13957732.58
      1877361.15     13957995.59
#Sta/Elev= 30
  4180.0 1868.54  4246.9 1831.95  4269.3 1825.51  4318.0 1822.84  4403.7 1810.56
  4456.6 1809.58  4730.8 1809.92  4840.6 1807.56  4879.4 1798.45  4970.1 1786.32
  4970.6 1785.82  4991.0 1786.32  5030.6 1787.81  5120.6 1798.12  5272.5 1802.61
  5345.8 1808.63  5408.1 1808.48  5509.7 1815.00  5553.8 1813.13  5570.1 1817.71
  5575.8 1814.40  5592.2 1821.13  5597.8 1817.66  5636.3 1830.90  5664.0 1827.20
  5686.0 1832.07  5702.4 1839.06  5708.0 1837.17  5724.4 1841.44  5779.5 1841.40
#Mann=8,-1,0
  4180.0     0.1       0  4269.3    0.07       0  4456.6   0.035       0
  4730.8    0.07       0  4970.1    0.05       0  4991.0    0.07       0
  5272.5   0.035       0  5408.1    0.07       0
Bank Sta=4970.1,4991
Exp/Cntr=0.3,0.1

Type RM Length L Ch R = 1,7080,273,273,273
BEGIN DESCRIPTION:
Fall Branch 12.0
END DESCRIPTION:
XS GIS Cut Line= 3
      1878824.98     13957175.01      1878025.00     13957525.00
      1877624.99     13957675.00
#Sta/Elev= 30
  4122.3 1937.72  4160.1 1933.76  4198.7 1918.64  4235.7 1900.35  4242.3 1894.38
  4288.0 1866.23  4340.6 1838.95  4358.1 1831.00  4372.3 1828.61  4532.8 1809.10
  4585.6 1806.62  4595.7 1805.99  4632.4 1803.74  4822.7 1802.53  4897.3 1803.05
  4910.9 1799.70  4928.8 1790.13  4951.8 1788.65  4957.7 1784.75  4994.8 1784.25
  4995.3 1783.75  5015.8 1784.25  5035.5 1790.23  5080.9 1794.89  5267.7 1800.38
  5327.5 1803.42  5352.4 1810.01  5377.3 1822.43  5389.1 1825.11  5422.7 1828.45
#Mann=10,-1,0
  4122.3     0.1       0  4372.3    0.07       0  4585.6   0.035       0
  4595.7    0.07       0  4632.4   0.035       0  4822.7    0.07       0
  4994.8    0.05       0  5015.8    0.07       0  5267.7   0.035       0
  5389.1    0.07       0
Bank Sta=4994.8,5015.8
Exp/Cntr=0.3,0.1

Type RM Length L Ch R = 1,6807,256,256,256
BEGIN DESCRIPTION:
Mapping XS cb450048
END DESCRIPTION:
XS GIS Cut Line= 3
      1878593.90     13957063.57      1877935.59     13957287.41
      1877308.65     13957388.08
#Sta/Elev= 30
  4262.9 1889.67  4264.9 1889.67  4280.2 1878.82  4304.0 1865.54  4311.6 1860.14
  4356.8 1836.45  4379.6 1825.40  4408.1 1815.75  4437.1 1808.77  4468.5 1804.32
  4513.7 1801.89  4620.1 1800.26  4758.2 1801.03  4907.7 1800.10  4927.2 1794.99
  4928.6 1784.36  4929.1 1783.86  4949.7 1784.36  4989.2 1784.65  4999.3 1788.33
  5019.6 1790.78  5141.1 1794.00  5218.0 1797.82  5262.7 1803.27  5282.9 1802.36
  5294.0 1803.13  5350.9 1810.01  5376.1 1811.25  5476.5 1819.31  5593.2 1830.57
#Mann=8,-1,0
  4262.9     0.1       0  4408.1   0.035       0  4513.7    0.07       0
  4928.6    0.05       0  4949.7    0.07       0  5218.0   0.035       0
  5376.1     0.1       0  5476.5    0.07       0
Bank Sta=4928.6,4949.7
Exp/Cntr=0.3,0.1

Type RM Length L Ch R = 1,6551,197,197,197
BEGIN DESCRIPTION:
Fall Branch 11.0
END DESCRIPTION:
XS GIS Cut Line= 3
      1878575.00     13956975.00      1877775.00     13957075.00
      1877375.03     13957075.00
#Sta/Elev= 30
  4198.5 1908.94  4228.7 1895.23  4316.9 1839.33  4322.0 1839.42  4329.5 1833.69
  4349.7 1824.09  4372.7 1815.94  4410.1 1807.23  4440.8 1804.47  4470.6 1801.24
  4500.8 1802.10  4558.8 1797.68  4702.4 1802.70  4720.0 1800.48  4783.0 1799.03
  4805.7 1802.50  4853.6 1796.19  4889.1 1795.07  4914.0 1795.07  4954.3 1786.35
  4974.0 1785.38  4974.5 1784.88  4995.1 1785.38  5021.0 1787.33  5094.7 1791.45
  5124.7 1802.81  5144.7 1807.28  5244.7 1813.62  5335.6 1816.36  5404.7 1818.99
#Mann=8,-1,0
  4198.5     0.1       0  4372.7   0.035       0  4440.8    0.07       0
  4889.1     0.1       0  4974.0    0.05       0  4995.1     0.1       0
  5021.0    0.07       0  5335.6   0.035       0
Bank Sta=4974,4995.1
Exp/Cntr=0.3,0.1

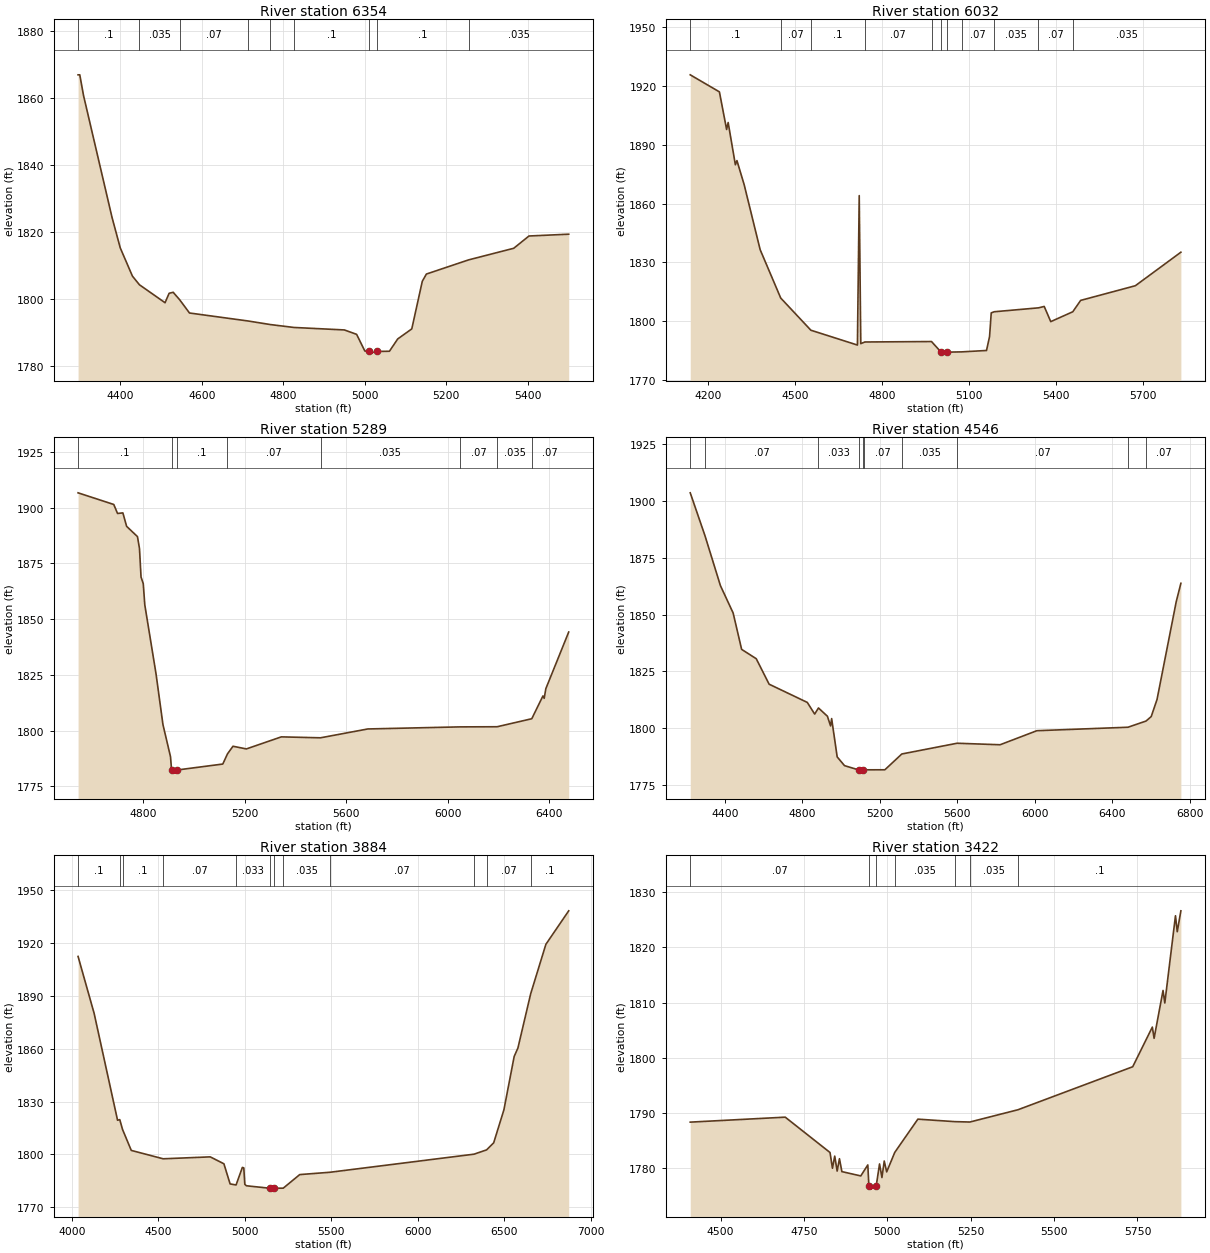
Type RM Length L Ch R = 1,6354,322,322,322
BEGIN DESCRIPTION:
Mapping XS e17f2b07
END DESCRIPTION:
XS GIS Cut Line= 3
      1878478.44     13956917.32      1877810.95     13956901.82
      1877278.24     13956966.55
#Sta/Elev= 30
  4296.1 1866.79  4300.3 1866.79  4309.5 1860.63  4379.6 1824.22  4399.6 1815.22
  4429.6 1806.78  4446.8 1804.21  4509.6 1798.86  4519.6 1801.68  4529.6 1801.97
  4545.4 1799.76  4569.6 1795.80  4713.4 1793.42  4768.4 1792.35  4826.0 1791.49
  4949.7 1790.75  4979.8 1789.44  5000.0 1784.47  5009.6 1784.34  5010.1 1783.84
  5030.7 1784.34  5060.4 1784.40  5080.6 1788.06  5115.2 1791.06  5141.0 1805.25
  5151.1 1807.41  5254.6 1811.63  5365.4 1815.09  5402.9 1818.75  5500.4 1819.29
#Mann=9,-1,0
  4296.1     0.1       0  4446.8   0.035       0  4545.4    0.07       0
  4713.4     0.1       0  4768.4    0.07       0  4826.0     0.1       0
  5009.6    0.05       0  5030.7     0.1       0  5254.6   0.035       0
Bank Sta=5009.6,5030.7
Exp/Cntr=0.3,0.1

Type RM Length L Ch R = 1,6032,743,743,743
BEGIN DESCRIPTION:
Fall Branch 10.0
END DESCRIPTION:
XS GIS Cut Line= 3
      1878624.99     13956925.00      1877825.00     13956625.00
      1877025.04     13956874.99
#Sta/Elev= 30
  4139.3 1925.67  4239.9 1916.98  4264.8 1897.79  4270.1 1901.34  4295.0 1879.78
  4300.4 1881.91  4325.3 1869.64  4380.5 1836.47  4451.4 1811.81  4555.4 1795.39
  4716.0 1787.82  4722.2 1864.04  4727.6 1788.53  4741.6 1789.38  4971.6 1789.61
  5004.6 1784.20  5005.1 1783.70  5025.8 1784.20  5075.9 1784.34  5161.3 1785.05
  5171.8 1792.10  5177.6 1804.23  5187.7 1804.80  5340.6 1806.80  5360.4 1807.51
  5382.9 1799.77  5458.9 1804.80  5486.1 1810.60  5674.7 1818.08  5831.8 1835.18
#Mann=11,-1,0
  4139.3     0.1       0  4451.4    0.07       0  4555.4     0.1       0
  4741.6    0.07       0  4971.6   0.033       0  5004.6   0.033       0
  5025.8   0.033       0  5075.9    0.07       0  5187.7   0.035       0
  5340.6    0.07       0  5458.9   0.035       0
Bank Sta=5004.6,5025.8
Exp/Cntr=0.3,0.1

Type RM Length L Ch R = 1,5289,743,743,743
BEGIN DESCRIPTION:
Fall Branch 9.0
END DESCRIPTION:
XS GIS Cut Line= 3
      1878619.54     13956756.65      1878371.59     13956401.61
      1876874.99     13956325.00
#Sta/Elev= 30
  4544.5 1906.68  4685.1 1901.45  4699.9 1897.42  4720.9 1897.68  4735.7 1891.64
  4778.3 1887.04  4786.3 1881.69  4792.4 1868.90  4801.1 1865.95  4807.2 1856.41
  4851.4 1825.48  4878.7 1802.68  4908.4 1788.28  4912.6 1782.31  4913.1 1781.81
  4933.8 1782.31  5114.3 1784.99  5132.7 1789.55  5154.4 1792.97  5207.1 1791.77
  5344.6 1797.18  5499.0 1796.76  5685.1 1800.73  6048.6 1801.66  6194.2 1801.72
  6330.7 1805.32  6374.6 1815.54  6379.6 1814.47  6386.0 1818.79  6476.1 1844.22
#Mann=8,-1,0
  4544.5     0.1       0  4912.6   0.033       0  4933.8     0.1       0
  5132.7    0.07       0  5499.0   0.035       0  6048.6    0.07       0
  6194.2   0.035       0  6330.7    0.07       0
Bank Sta=4912.6,4933.8
Exp/Cntr=0.3,0.1

Type RM Length L Ch R = 1,4546,662,662,662
BEGIN DESCRIPTION:
Fall Branch 8.0
END DESCRIPTION:
XS GIS Cut Line= 3
      1879225.02     13956175.01      1878577.37     13955826.08
      1876824.97     13956225.01
#Sta/Elev= 30
  4222.0 1903.67  4298.2 1884.74  4377.8 1862.76  4443.5 1850.69  4487.3 1834.66
  4562.8 1830.53  4629.2 1819.31  4826.3 1811.27  4864.4 1806.13  4884.0 1808.82
  4930.1 1805.18  4946.4 1800.92  4952.0 1804.14  4980.6 1787.25  5018.4 1783.40
  5092.9 1781.48  5093.4 1780.98  5114.4 1781.48  5120.8 1781.56  5226.7 1781.57
  5314.3 1788.54  5599.5 1793.27  5821.6 1792.61  6011.4 1798.80  6481.8 1800.33
  6575.0 1803.06  6601.7 1805.03  6631.8 1812.58  6730.8 1855.66  6754.9 1863.79
#Mann=10,-1,0
  4222.0     0.1       0  4298.2    0.07       0  4884.0   0.033       0
  5092.9   0.033       0  5114.4   0.033       0  5120.8    0.07       0
  5314.3   0.035       0  5599.5    0.07       0  6481.8   0.035       0
  6575.0    0.07       0
Bank Sta=5092.9,5114.4
Exp/Cntr=0.3,0.1

Type RM Length L Ch R = 1,3884,462,462,462
BEGIN DESCRIPTION:
Fall Branch 7.0
END DESCRIPTION:
XS GIS Cut Line= 3
      1878975.00     13954825.00      1878203.22     13955401.95
      1876574.97     13956325.02
#Sta/Elev= 30
  4036.5 1912.42  4129.3 1880.11  4264.7 1819.43  4277.5 1819.78  4293.5 1814.20
  4343.9 1802.31  4528.2 1797.55  4800.4 1798.64  4879.3 1794.71  4915.0 1783.30
  4949.5 1782.69  4985.9 1792.65  4994.2 1792.40  5000.1 1783.04  5009.5 1782.23
  5144.9 1780.83  5145.4 1780.33  5166.6 1780.83  5222.2 1780.88  5317.4 1788.58
  5491.9 1789.90  6324.7 1800.17  6397.0 1802.60  6438.2 1806.61  6497.4 1825.39
  6556.6 1855.62  6578.2 1860.41  6652.0 1891.22  6739.8 1919.29  6871.8 1938.31
#Mann=12,-1,0
  4036.5     0.1       0  4277.5   0.035       0  4293.5     0.1       0
  4528.2    0.07       0  4949.5   0.033       0  5144.9   0.033       0
  5166.6   0.033       0  5222.2   0.035       0  5491.9    0.07       0
  6324.7   0.035       0  6397.0    0.07       0  6652.0     0.1       0
Bank Sta=5144.9,5166.6
Exp/Cntr=0.3,0.1

Type RM Length L Ch R = 1,3422,630,630,630
BEGIN DESCRIPTION:
Fall Branch 6.0
END DESCRIPTION:
XS GIS Cut Line= 3
      1878256.94     13954964.37      1877780.41     13955414.87
      1877004.35     13955664.87
#Sta/Elev= 30
  4409.0 1788.37  4693.8 1789.27  4828.1 1782.87  4835.4 1780.02  4842.2 1782.22
  4849.5 1779.51  4856.4 1781.75  4863.7 1779.41  4920.3 1778.63  4941.4 1780.62
  4944.7 1776.74  4945.2 1776.24  4966.4 1776.74  4976.6 1780.80  4983.8 1778.34
  4990.7 1781.33  4998.0 1779.36  5022.2 1782.89  5091.5 1788.91  5201.8 1788.46
  5247.4 1788.39  5391.5 1790.61  5735.7 1798.40  5794.5 1805.58  5799.8 1803.55
  5826.6 1812.21  5831.9 1809.94  5863.9 1825.74  5869.2 1822.85  5880.1 1826.63
#Mann=7,-1,0
  4409.0    0.07       0  4944.7    0.05       0  4966.4    0.07       0
  5022.2   0.035       0  5201.8    0.07       0  5247.4   0.035       0
  5391.5     0.1       0
Bank Sta=4944.7,4966.4
Exp/Cntr=0.3,0.1

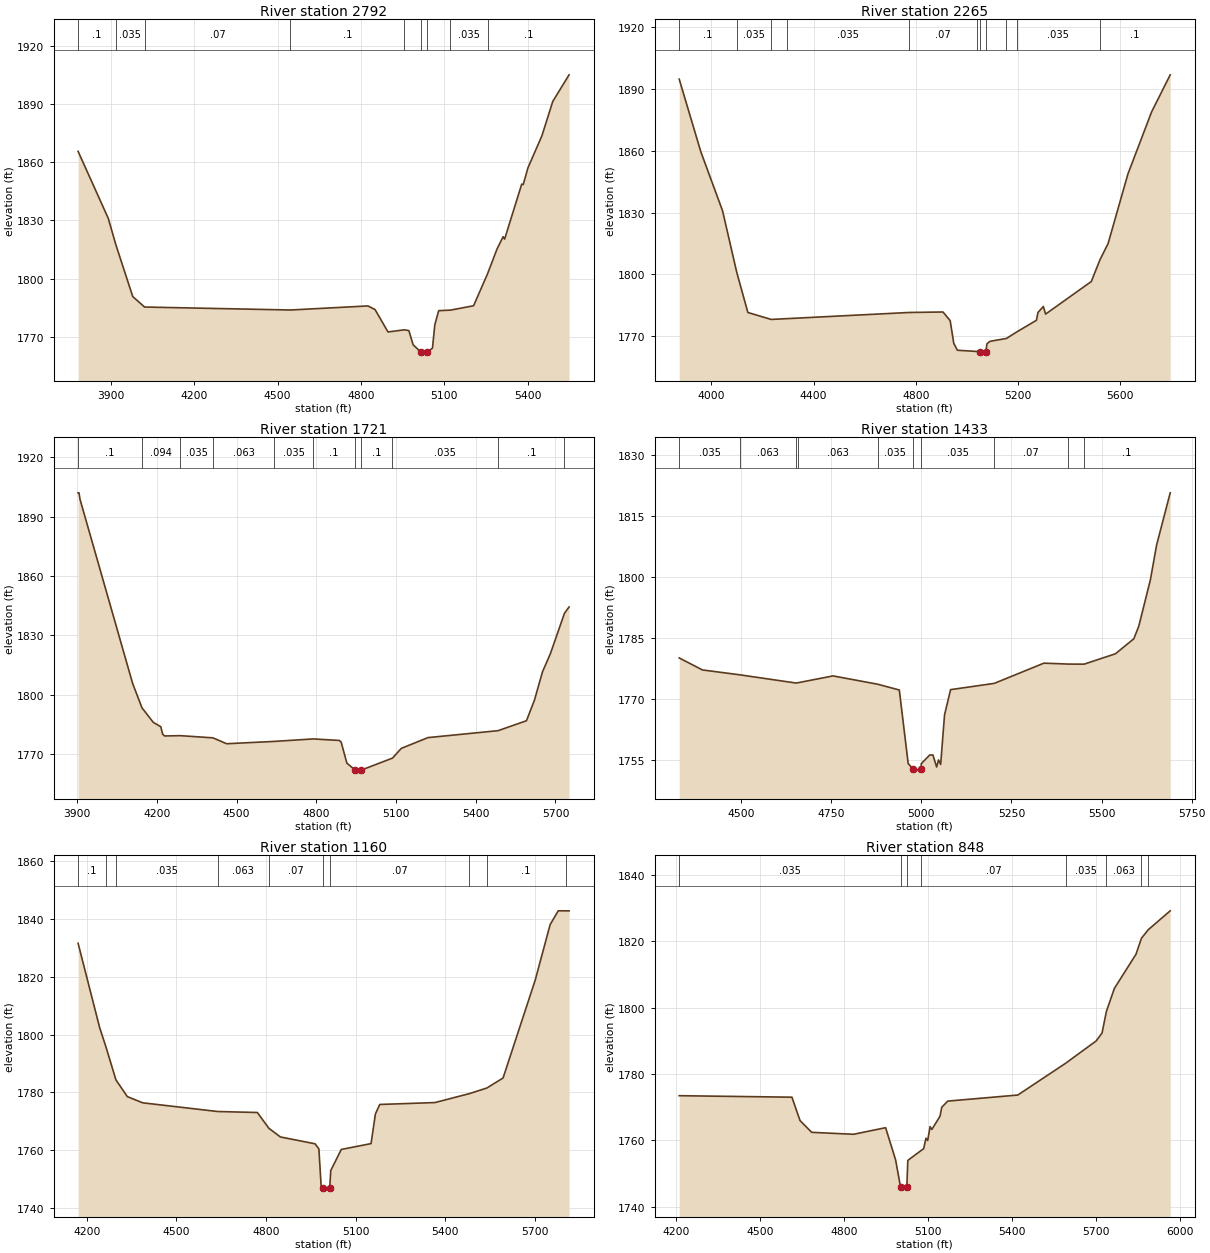
Type RM Length L Ch R = 1,2792,527,527,527
BEGIN DESCRIPTION:
Fall Branch 5.0
END DESCRIPTION:
XS GIS Cut Line= 3
      1878845.55     13954572.84      1877675.00     13954875.00
      1877175.04     13955124.98
#Sta/Elev= 30
  3781.6 1865.54  3890.4 1830.98  3917.2 1817.62  3978.4 1790.76  4021.0 1785.35
  4546.2 1783.82  4825.3 1785.92  4850.8 1784.06  4897.6 1772.51  4956.9 1773.63
  4972.8 1773.18  4987.9 1765.94  5016.0 1762.11  5016.5 1761.61  5037.8 1762.11
  5057.6 1764.16  5066.0 1776.11  5080.0 1783.48  5122.4 1783.76  5205.7 1786.01
  5255.8 1802.40  5289.6 1815.07  5312.0 1821.58  5317.5 1820.35  5379.0 1848.65
  5384.6 1848.47  5401.4 1857.04  5451.7 1873.54  5490.8 1891.24  5549.5 1904.94
#Mann=9,-1,0
  3781.6     0.1       0  3917.2   0.035       0  4021.0    0.07       0
  4546.2     0.1       0  4956.9    0.07       0  5016.0    0.05       0
  5037.8    0.07       0  5122.4   0.035       0  5255.8     0.1       0
Bank Sta=5016,5037.8
Exp/Cntr=0.3,0.1

Type RM Length L Ch R = 1,2265,544,544,544
BEGIN DESCRIPTION:
Fall Branch 4.0
END DESCRIPTION:
XS GIS Cut Line= 3
      1878424.98     13953625.02      1877625.00     13954425.00
      1877175.01     13955074.99
#Sta/Elev= 30
  3873.9 1894.82  3958.7 1859.47  4043.6 1830.82  4099.0 1800.97  4142.6 1781.41
  4233.8 1778.03  4297.6 1778.43  4772.8 1781.41  4906.3 1781.65  4934.5 1777.44
  4948.7 1766.37  4962.8 1763.05  5037.8 1762.47  5052.5 1762.15  5053.0 1761.65
  5074.3 1762.15  5078.2 1766.15  5090.4 1767.39  5154.8 1768.79  5195.3 1771.97
  5272.1 1777.61  5278.2 1781.42  5299.2 1784.33  5308.0 1780.62  5487.0 1796.47
  5520.6 1806.97  5552.6 1814.90  5630.3 1848.75  5722.8 1878.88  5795.8 1896.95
#Mann=11,-1,0
  3873.9     0.1       0  4099.0   0.035       0  4233.8    0.07       0
  4297.6   0.035       0  4772.8    0.07       0  5037.8     0.1       0
  5052.5    0.05       0  5074.3     0.1       0  5154.8    0.07       0
  5195.3   0.035       0  5520.6     0.1       0
Bank Sta=5052.5,5074.3
Exp/Cntr=0.3,0.1

Type RM Length L Ch R = 1,1721,288,288,288
BEGIN DESCRIPTION:
Fall Branch 3.0
END DESCRIPTION:
XS GIS Cut Line= 3
      1878225.00     13953225.00      1877425.00     13953975.00
      1876675.04     13954025.00
#Sta/Elev= 30
  3903.1 1902.04  3906.5 1902.04  3910.2 1898.83  4108.5 1805.75  4143.6 1793.48
  4186.2 1786.14  4214.5 1783.91  4221.3 1780.20  4228.6 1779.27  4288.0 1779.42
  4410.8 1778.32  4462.1 1775.34  4642.2 1776.52  4788.0 1777.77  4886.6 1777.00
  4893.4 1776.14  4914.9 1765.54  4946.4 1762.01  4946.9 1761.51  4968.4 1762.01
  5086.5 1768.07  5119.9 1773.01  5220.2 1778.44  5484.2 1781.94  5591.0 1786.96
  5621.1 1797.41  5651.1 1811.59  5681.2 1820.91  5734.0 1841.23  5751.3 1844.41
#Mann=11,-1,0
  3903.1     0.1       0  4143.6   0.094       0  4288.0   0.035       0
  4410.8   0.063       0  4642.2   0.035       0  4788.0     0.1       0
  4946.4    0.05       0  4968.4     0.1       0  5086.5   0.035       0
  5484.2     0.1       0  5734.0    0.07       0
Bank Sta=4946.4,4968.4
Exp/Cntr=0.3,0.1

Type RM Length L Ch R = 1,1433,273,273,273
BEGIN DESCRIPTION:
Fall Branch 2.1
END DESCRIPTION:
XS GIS Cut Line= 4
      1877936.63     13953347.18      1877592.91     13953617.99
      1877298.64     13953732.58      1876718.99     13953917.13
#Sta/Elev= 30
  4328.8 1780.05  4393.1 1777.10  4497.4 1775.89  4652.6 1773.88  4657.5 1773.94
  4755.4 1775.63  4879.5 1773.58  4939.2 1772.16  4963.8 1754.08  4977.3 1752.70
  4977.8 1752.20  4999.3 1752.70  5000.2 1754.05  5023.5 1756.17  5032.4 1756.18
  5042.7 1753.21  5048.0 1754.96  5053.9 1753.85  5064.6 1766.03  5081.4 1772.25
  5202.5 1773.79  5340.2 1778.77  5407.8 1778.54  5451.7 1778.52  5538.8 1781.08
  5589.7 1784.78  5603.3 1787.85  5635.5 1799.27  5652.7 1807.81  5690.5 1820.68
#Mann=10,-1,0
  4328.8   0.035       0  4497.4   0.063       0  4652.6   0.035       0
  4657.5   0.063       0  4879.5   0.035       0  4977.3   0.035       0
  4999.3   0.035       0  5202.5    0.07       0  5407.8   0.035       0
  5451.7     0.1       0
Bank Sta=4977.3,4999.3
Exp/Cntr=0.3,0.1

Type RM Length L Ch R = 1,1160,312,312,312
BEGIN DESCRIPTION:
Fall Branch 2.0
END DESCRIPTION:
XS GIS Cut Line= 3
      1878075.03     13953274.99      1877275.00     13953475.00
      1876625.01     13953974.99
#Sta/Elev= 30
  4170.6 1831.61  4242.8 1802.42  4263.4 1795.89  4297.4 1784.30  4335.6 1778.51
  4387.1 1776.36  4638.3 1773.35  4771.1 1773.01  4809.7 1767.55  4848.4 1764.54
  4964.3 1762.18  4977.2 1760.42  4984.9 1747.35  4991.5 1746.98  4992.0 1746.48
  5013.5 1746.98  5017.0 1752.92  5052.3 1760.22  5152.0 1762.24  5166.5 1772.47
  5181.0 1775.79  5365.9 1776.45  5481.7 1779.55  5540.0 1781.49  5594.2 1784.96
  5701.8 1818.81  5751.9 1838.07  5779.0 1842.83  5803.6 1842.83  5815.3 1842.81
#Mann=10,-1,0
  4170.6     0.1       0  4263.4   0.094       0  4297.4   0.035       0
  4638.3   0.063       0  4809.7    0.07       0  4991.5    0.05       0
  5013.5    0.07       0  5481.7   0.035       0  5540.0     0.1       0
  5803.6    0.07       0
Bank Sta=4991.5,5013.5
Exp/Cntr=0.3,0.1

Type RM Length L Ch R = 1,848,0,0,0
BEGIN DESCRIPTION:
Fall Branch 1.0
END DESCRIPTION:
XS GIS Cut Line= 3
      1877779.67     13952725.77      1877186.99     13953177.94
      1876375.03     13953774.98
#Sta/Elev= 30
  4212.3 1773.48  4614.7 1773.03  4643.7 1765.98  4685.4 1762.43  4835.0 1761.84
  4949.3 1763.83  4985.1 1754.09  5002.9 1745.80  5003.4 1745.30  5025.0 1745.80
  5028.6 1753.96  5076.8 1757.00  5085.0 1757.47  5093.4 1760.65  5099.6 1759.97
  5108.1 1764.15  5114.3 1763.28  5143.6 1767.28  5149.8 1770.00  5171.2 1771.85
  5421.4 1773.68  5592.1 1783.26  5701.4 1790.01  5722.2 1792.39  5737.6 1798.86
  5766.2 1805.84  5843.4 1816.14  5862.9 1820.96  5887.3 1823.55  5965.6 1829.24
#Mann=8,-1,0
  4212.3   0.035       0  5002.9   0.035       0  5025.0   0.035       0
  5076.8    0.07       0  5592.1   0.035       0  5737.6   0.063       0
  5862.9   0.035       0  5887.3   0.063       0
Bank Sta=5002.9,5025
Exp/Cntr=0.3,0.1

Chan Stop Cuts=-1