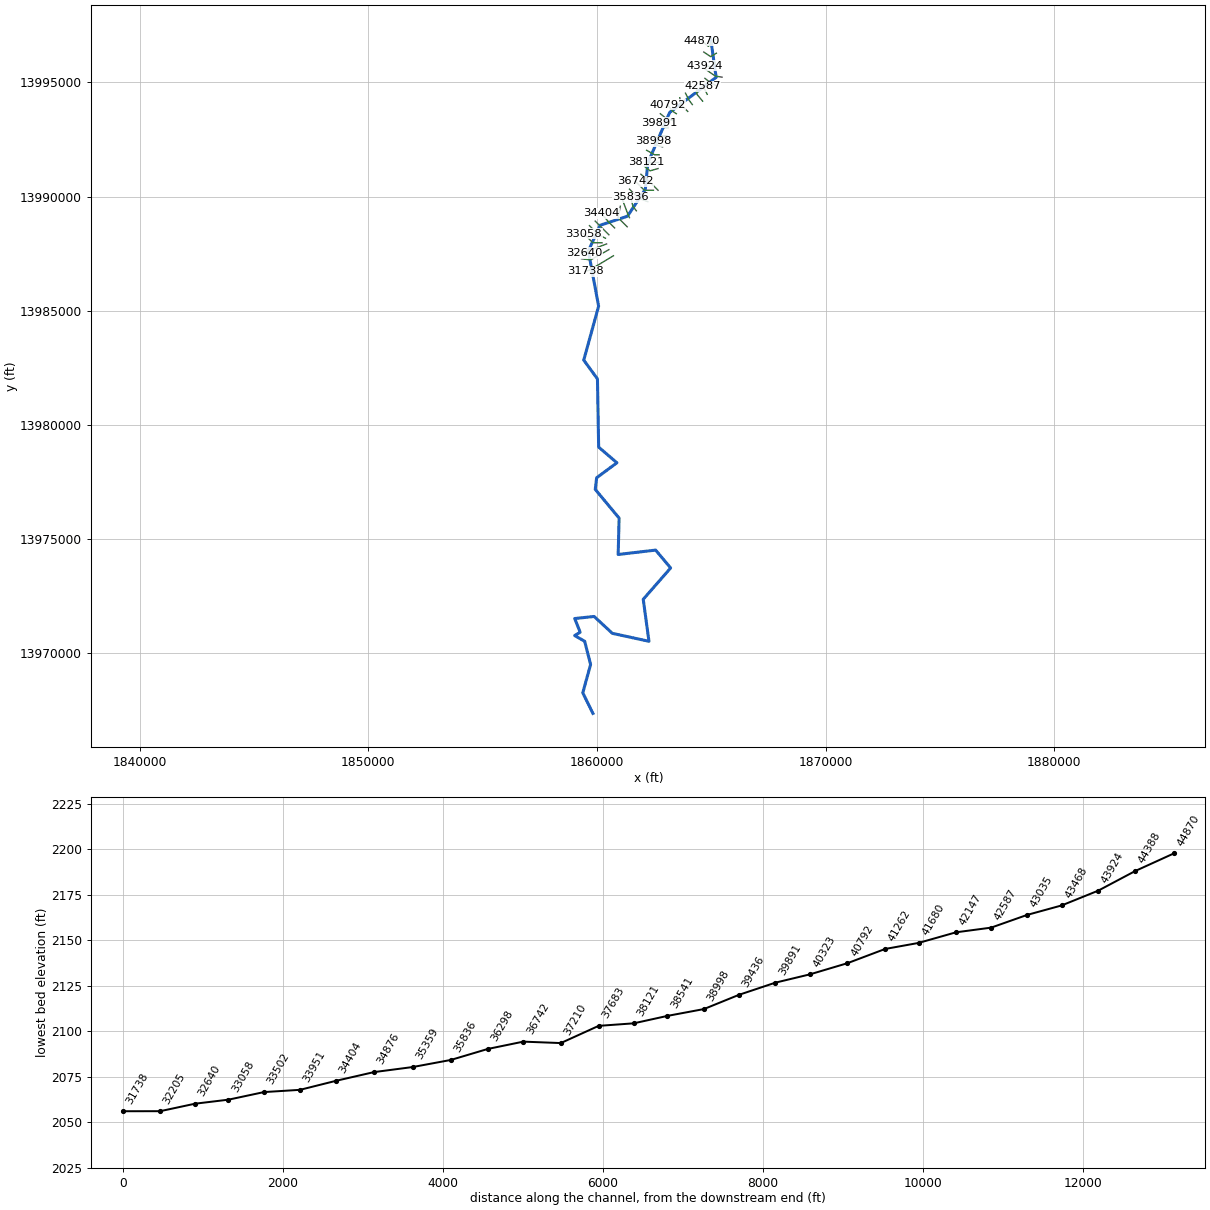
--- Fessenden Branch.prj (project) ---

Proj Title=Fessenden Branch Base Level Engineering
Current Plan=p01
Default Exp/Contr=0.3,0.1
English Units
Geom File=g01
Flow File=f01
Plan File=p01
Y Axis Title=Elevation
X Axis Title(PF)=Main Channel Distance
X Axis Title(XS)=Station
BEGIN DESCRIPTION:
Fessenden Branch
END DESCRIPTION:
DSS Export Rating Curves= 0
DSS Export Rating Curve Sorted= 0
DSS Export Volume Flow Curves= 0
DXF OffsetX= 0
DXF OffsetY= 0
DXF ScaleX= 1
DXF ScaleY= 10

--- Fessenden Branch.p01 (plan) ---

Plan Title=Multiple Run
Short Identifier=Multiple
Geom File=g01
Flow File=f01
Subcritical Flow
K Sum by GR= 0
Std Step Tol= 0.01
Critical Tol= 0.01
Num of Std Step Trials= 20
Max Error Tol= 0.3
Flow Tol Ratio= 0.001
Split Flow NTrial= 30
Split Flow Tol= 0.02
Split Flow Ratio= 0.02
Log Output Level= 0
Friction Slope Method= 1
Unsteady Friction Slope Method= 2
Unsteady Bridges Friction Slope Method= 1
Parabolic Critical Depth
Global Vel Dist=  1 , 1 , 1
Global Log Level= 0
CheckData=True
Encroach Param= -1, 0, 0, 0
BEGIN DESCRIPTION:
Multiple Run
END DESCRIPTION:

--- Fessenden Branch.f01 (steady flow) ---

Flow Title=Multiple
Number of Profiles=7
Profile Names=10-year,25-year,50-year,1pct_min,100-year,1pct_plu,500-year
River Rch & RM= Fessenden Branch,Reach-1,44870
     201     304     392     246     490     978     754
River Rch & RM= Fessenden Branch,Reach-1,43468
    1214    2085    2918    1972    3935    7852    7076
River Rch & RM= Fessenden Branch,Reach-1,38998
    1739    3038    4298    2932    5851   11673   10724
River Rch & RM= Fessenden Branch,Reach-1,33951
    2301    4071    5808    3991    7962   15887   14810
River Rch & RM= Fessenden Branch,Reach-1,30336
    2689    4791    6870    4741    9459   18874   17754
River Rch & RM= Fessenden Branch,Reach-1,28485
    2889    5162    7415    5125   10225   20402   19250
River Rch & RM= Fessenden Branch,Reach-1,27637
    3100    5552    7986    5526   11026   22000   20808
River Rch & RM= Fessenden Branch,Reach-1,25628
    3297    5913    8514    5895   11763   23470   22227
River Rch & RM= Fessenden Branch,Reach-1,21670
    4154    7485   10814    7509   14982   29893   28455
River Rch & RM= Fessenden Branch,Reach-1,15274
    4288    7736   11184    7771   15505   30936   29485
River Rch & RM= Fessenden Branch,Reach-1,13636
    4586    8280   11977    8323   16607   33136   31593
River Rch & RM= Fessenden Branch,Reach-1,5911
    4820    8720   12631    8789   17536   34989   33446
Boundary for River Rch & Prof#=Fessenden Branch,Reach-1,1
Up Type=0
Dn Type=3
Dn Slope=0.005
Boundary for River Rch & Prof#=Fessenden Branch,Reach-1,2
Up Type=0
Dn Type=3
Dn Slope=0.005
Boundary for River Rch & Prof#=Fessenden Branch,Reach-1,3
Up Type=0
Dn Type=3
Dn Slope=0.005
Boundary for River Rch & Prof#=Fessenden Branch,Reach-1,4
Up Type=0
Dn Type=3
Dn Slope=0.005
Boundary for River Rch & Prof#=Fessenden Branch,Reach-1,5
Up Type=0
Dn Type=3
Dn Slope=0.005
Boundary for River Rch & Prof#=Fessenden Branch,Reach-1,6
Up Type=0
Dn Type=3
Dn Slope=0.005
Boundary for River Rch & Prof#=Fessenden Branch,Reach-1,7
Up Type=0
Dn Type=3
Dn Slope=0.005

--- Fessenden Branch.g01 (geometry) ---

Geom Title=Existing Conditions
Program Version=4.10

River Reach=Fessenden Branch,Reach-1
Reach XY= 30
        1864975.       13996925.      1865215.86     13995218.27
      1863185.61     13993685.06      1862227.23     13991469.07
      1862119.48     13990322.57      1861334.71     13989135.75
      1860141.44     13988741.79      1859625.94     13987614.52
       1860075.2     13985199.92      1859425.51     13982840.21
      1860024.45     13982013.92      1860076.62     13979031.04
      1860875.64     13978345.05      1859988.47     13977688.57
      1859927.07     13977180.86      1860971.45     13975923.53
      1860930.61     13974330.59      1862569.07     13974522.76
      1863225.49      13973740.2      1862027.06     13972369.15
      1862277.47     13970530.45      1860676.47     13970878.53
      1859878.34     13971617.01      1859030.11     13971527.32
      1859267.82     13970924.67      1859026.58     13970781.09
       1859465.7      13970531.7      1859723.96     13969514.56
      1859382.56       13968275.        1859825.       13967375.

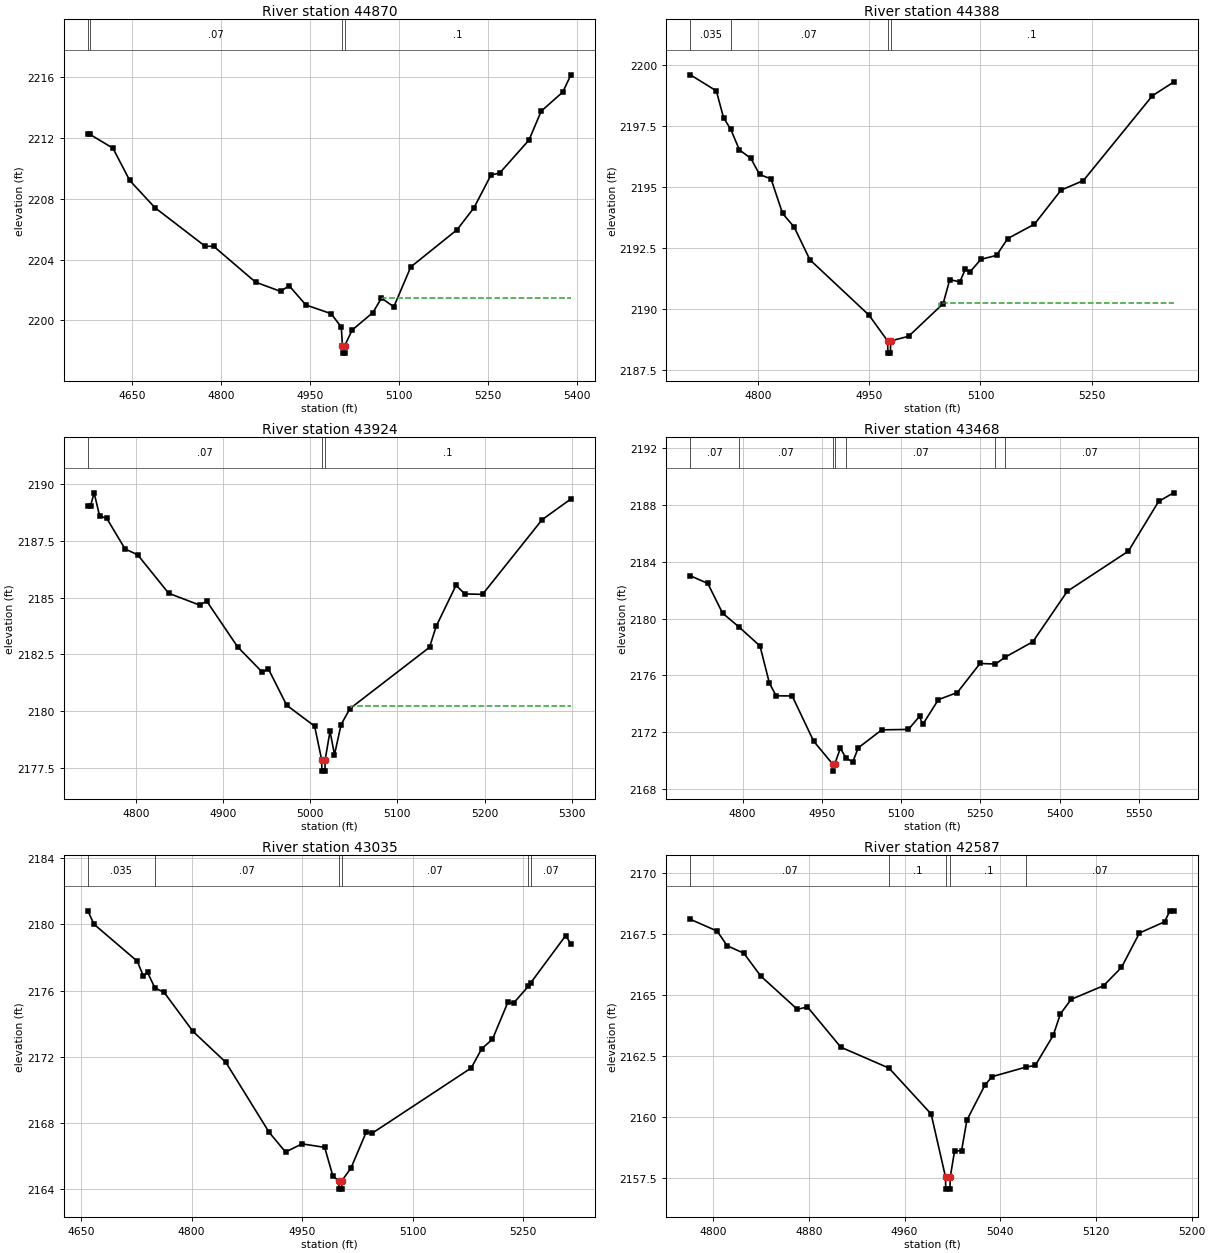
Type RM Length L Ch R = 1 ,44870   ,482,482,482
BEGIN DESCRIPTION:
Fessenden Branch 96.0
END DESCRIPTION:
XS GIS Cut Line= 3
      1865175.02     13996875.02        1864875.       13996575.
        1864575.       13996825.
#Sta/Elev= 30
  4575.6 2212.24  4579.3 2212.24    4618 2211.33  4646.3 2209.21  4688.8 2207.42
  4773.6 2204.88  4787.8 2204.88  4858.5 2202.52  4900.9 2201.91    4915 2202.29
  4943.3 2201.02  4985.7 2200.45  5003.1 2199.57    5005 2198.35  5005.3 2197.85
  5008.8 2197.85    5009 2198.35  5021.4 2199.37  5056.5 2200.52  5070.8 2201.47
  5091.7  2200.9  5120.3 2203.52  5198.4 2205.97    5227 2207.42  5255.7 2209.58
    5270 2209.69  5319.5 2211.86  5340.3 2213.77  5376.7 2215.03  5390.4 2216.16
#Mann= 4 ,-1 , 0
  4575.6    .035       0  4579.3     .07       0    5005     .05       0
    5009      .1       0
#XS Ineff= 2 , 0
                         5071.83         2201.49
Permanent Ineff=
       F       F
Bank Sta=5005,5009
XS Rating Curve= 0 ,0
Exp/Cntr=0.3,0.1

Type RM Length L Ch R = 1 ,44388   ,464,464,464
BEGIN DESCRIPTION:
Fessenden Branch 95.0
END DESCRIPTION:
XS GIS Cut Line= 3
      1865224.98     13996274.99        1864975.       13996125.
      1864674.99     13996325.01
#Sta/Elev= 30
  4708.5 2199.61  4743.5 2198.95  4753.2 2197.85    4763 2197.37  4774.6 2196.53
  4790.1 2196.18  4801.8 2195.52  4817.3 2195.34  4832.9 2193.92  4848.4 2193.37
  4869.8 2192.02  4949.5 2189.75  4974.7 2188.69    4975 2188.19  4978.5 2188.19
  4978.7 2188.69    5003 2188.88  5049.6 2190.22  5058.6 2191.21  5072.1 2191.11
  5079.7 2191.64  5085.7 2191.52  5100.7 2192.04  5121.7  2192.2  5136.7 2192.89
  5172.8 2193.48  5208.8 2194.88  5238.9 2195.27    5332 2198.75  5360.6 2199.31
#Mann= 4 ,-1 , 0
  4708.5    .035       0    4763     .07       0  4974.7     .05       0
  4978.7      .1       0
#XS Ineff= 2 , 0
                         5043.67         2190.24
Permanent Ineff=
       F       F
Bank Sta=4974.7,4978.7
XS Rating Curve= 0 ,0
Exp/Cntr=0.3,0.1

Type RM Length L Ch R = 1 ,43924   ,456,456,456
BEGIN DESCRIPTION:
Fessenden Branch 94.0
END DESCRIPTION:
XS GIS Cut Line= 3
      1865174.97     13995874.96        1865025.       13995675.
      1864724.99       13995725.
#Sta/Elev= 30
  4744.9 2189.03    4748 2189.03  4752.1 2189.61  4758.4  2188.6  4766.7 2188.48
  4787.6 2187.14  4802.1 2186.88  4837.6 2185.19    4873 2184.67  4881.3 2184.84
  4916.7 2182.83  4944.9 2181.72  4952.1 2181.85    4973 2180.26    5005 2179.34
  5013.1 2177.86  5013.4 2177.36  5016.9 2177.36  5017.1 2177.86  5022.7 2179.12
  5027.8 2178.08  5035.4 2179.41  5045.5 2180.11  5136.8 2182.81  5144.4 2183.73
  5167.2 2185.54  5177.3 2185.16  5197.6 2185.14    5266 2188.43    5299 2189.34
#Mann= 3 ,-1 , 0
  4744.9     .07       0  5013.1     .05       0  5017.1      .1       0
#XS Ineff= 2 , 0
                         5046.51         2180.21
Permanent Ineff=
       F       F
Bank Sta=5013.1,5017.1
XS Rating Curve= 0 ,0
Exp/Cntr=0.3,0.1

Type RM Length L Ch R = 1 ,43468   ,433,433,433
BEGIN DESCRIPTION:
Fessenden Branch 93.0
END DESCRIPTION:
XS GIS Cut Line= 3
      1865474.95     13995225.01        1865175.       13995275.
      1864675.01     13995624.99
#Sta/Elev= 30
  4701.3 2183.02  4734.2 2182.48  4762.1 2180.39  4793.6  2179.4    4833 2178.07
  4850.8 2175.45  4863.5 2174.56  4893.9 2174.55  4934.4 2171.37  4970.4 2169.75
  4970.7 2169.25  4974.4 2169.75  4985.1 2170.86  4995.5  2170.2  5008.4 2169.88
  5018.9 2170.89  5063.4 2172.16  5113.9 2172.19  5134.9 2173.11    5141 2172.54
  5170.6 2174.29  5206.4 2174.79  5249.5 2176.84  5278.6  2176.8  5297.3 2177.29
  5349.4 2178.37  5414.7 2181.93  5530.3 2184.76  5587.4 2188.26  5615.7 2188.87
#Mann= 7 ,-1 , 0
  4701.3     .07       0  4793.6     .07       0  4970.4     .05       0
  4974.4     .07       0  4995.5     .07       0  5278.6      .1       0
  5297.3     .07       0
Bank Sta=4970.4,4974.4
XS Rating Curve= 0 ,0
Exp/Cntr=0.3,0.1

Type RM Length L Ch R = 1 ,43035   ,448,448,448
BEGIN DESCRIPTION:
Fessenden Branch 92.0
END DESCRIPTION:
XS GIS Cut Line= 3
      1865275.01       13994825.        1864975.       13994975.
      1864724.98     13995175.02
#Sta/Elev= 30
  4659.2 2180.81  4667.6    2180  4726.3 2177.77  4734.7 2176.86  4740.3 2177.09
  4750.3 2176.15  4762.6  2175.9  4801.8 2173.54  4846.5 2171.67  4905.2 2167.45
  4927.5 2166.26  4949.9 2166.75  4980.6 2166.54  4991.8  2164.8  4999.8 2164.52
  5000.1 2164.02  5003.6 2164.02  5003.8 2164.52  5016.2 2165.28    5037 2167.46
    5045 2167.39  5179.5 2171.33  5193.9  2172.5  5208.3 2173.06  5229.1 2175.28
  5237.1 2175.25  5256.9 2176.25  5260.5 2176.48  5307.6 2179.31  5314.8 2178.82
#Mann= 6 ,-1 , 0
  4659.2    .035       0  4750.3     .07       0  4999.8     .05       0
  5003.8     .07       0  5256.9      .1       0  5260.5     .07       0
Bank Sta=4999.8,5003.8
XS Rating Curve= 0 ,0
Exp/Cntr=0.3,0.1

Type RM Length L Ch R = 1 ,42587   ,440,440,440
BEGIN DESCRIPTION:
Fessenden Branch 91.0
END DESCRIPTION:
XS GIS Cut Line= 3
      1864824.98     13994475.03        1864725.       13994675.
      1864625.03     13994824.96
#Sta/Elev= 30
    4781 2168.11  4803.3 2167.63  4811.7 2167.03  4825.7 2166.72  4839.7 2165.79
  4870.4 2164.42  4878.8 2164.52  4906.7 2162.87    4947 2162.01  4982.2 2160.13
  4994.2 2157.55  4994.4 2157.05  4997.9 2157.05  4998.2 2157.55  5001.8 2158.62
  5007.6 2158.62  5012.1 2159.88  5027.1 2161.31  5033.1 2161.66  5061.9 2162.06
  5069.2 2162.12  5084.2 2163.35  5090.2 2164.23  5099.2 2164.83  5126.3 2165.39
  5141.3 2166.14  5156.3 2167.55  5177.3 2168.01  5181.8 2168.46  5184.8 2168.46
#Mann= 5 ,-1 , 0
    4781     .07       0    4947      .1       0  4994.2     .05       0
  4998.2      .1       0  5061.9     .07       0
Bank Sta=4994.2,4998.2
XS Rating Curve= 0 ,0
Exp/Cntr=0.3,0.1

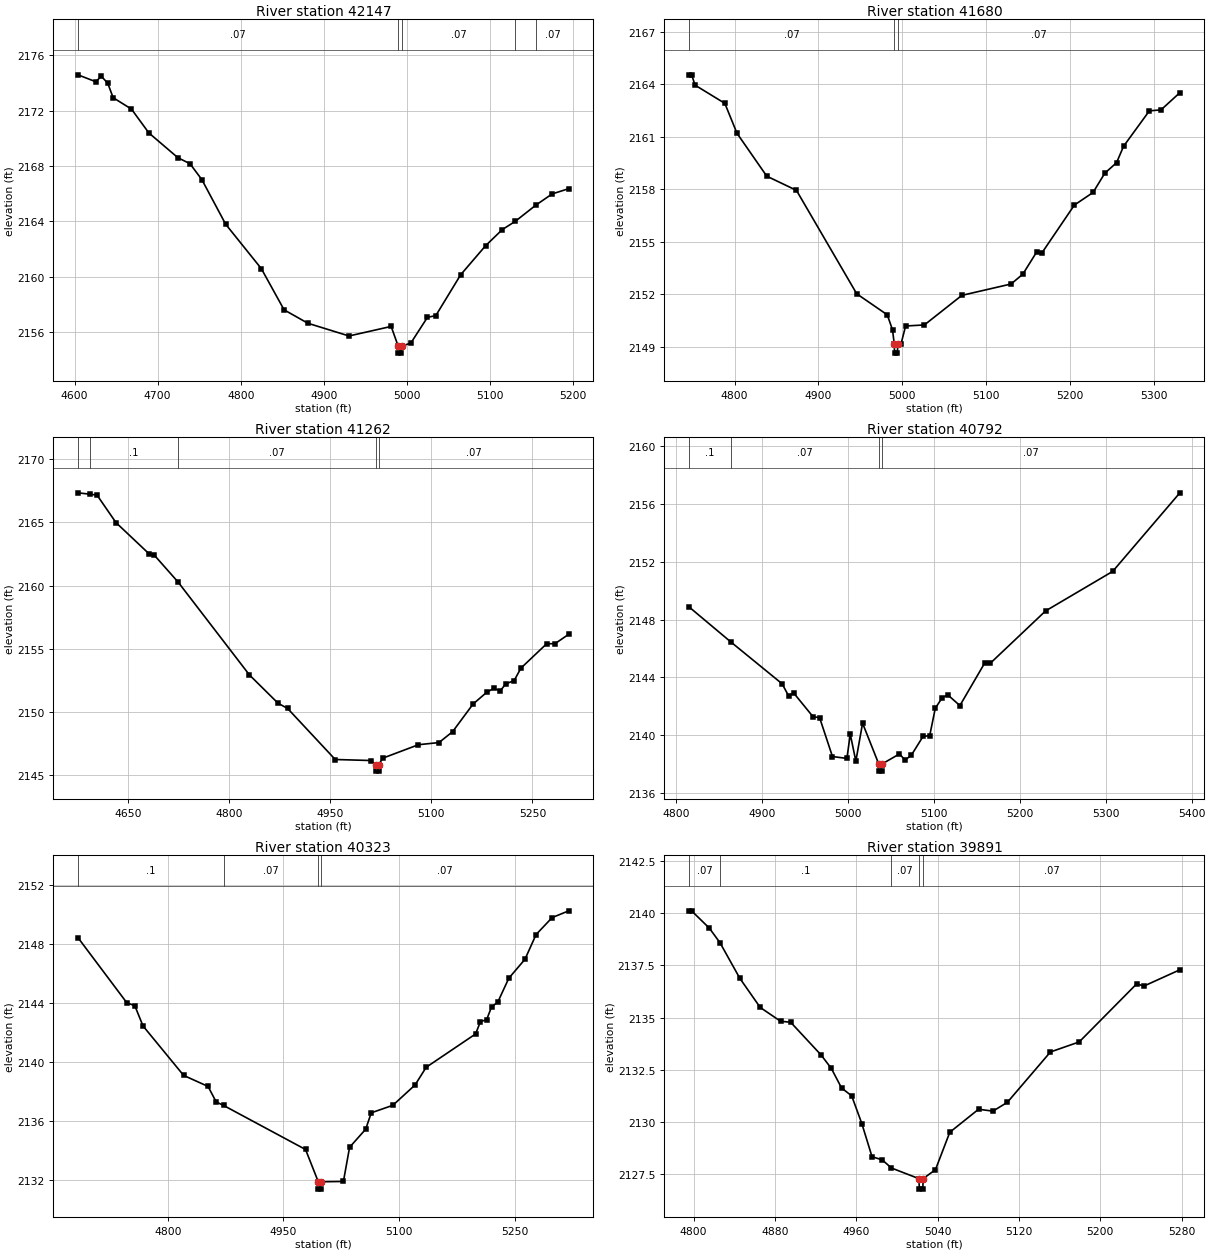
Type RM Length L Ch R = 1 ,42147   ,467,467,467
BEGIN DESCRIPTION:
Fessenden Branch 90.0
END DESCRIPTION:
XS GIS Cut Line= 3
        1864625.       13994175.        1864375.       13994475.
        1864375.     13994674.99
#Sta/Elev= 30
  4604.1 2174.59  4625.6 2174.09  4632.1 2174.49  4639.9 2173.99  4646.4 2172.94
  4668.5 2172.11  4689.4 2170.39  4724.5 2168.59  4738.8 2168.17  4753.1 2167.02
  4781.8 2163.79  4824.7 2160.58  4852.1  2157.6  4880.7 2156.63  4930.2 2155.71
  4980.9  2156.4  4989.4 2154.97  4989.6 2154.47  4993.1 2154.47  4993.4 2154.97
  5004.6  2155.2  5024.6 2157.06  5034.6 2157.18  5064.6 2160.14  5094.6 2162.24
  5114.6  2163.4  5130.5 2164.01    5155 2165.17  5174.6 2165.98  5194.6 2166.36
#Mann= 5 ,-1 , 0
  4604.1     .07       0  4989.4     .05       0  4993.4     .07       0
  5130.5      .1       0    5155     .07       0
Bank Sta=4989.4,4993.4
XS Rating Curve= 0 ,0
Exp/Cntr=0.3,0.1

Type RM Length L Ch R = 1 ,41680   ,418,418,418
BEGIN DESCRIPTION:
Fessenden Branch 89.0
END DESCRIPTION:
XS GIS Cut Line= 3
      1864174.97     13994025.04        1864025.       13994225.
      1863874.98     13994525.04
#Sta/Elev= 30
  4745.7 2164.54  4748.8 2164.54  4752.9 2163.95  4788.4 2162.91  4802.9  2161.2
  4838.4 2158.75  4873.8 2157.94  4945.7 2152.03  4982.1 2150.83  4988.4 2149.97
  4990.5 2149.14  4990.8 2148.64  4994.3 2148.64  4994.5 2149.14  4998.4 2149.14
    5004 2150.19  5026.4 2150.25  5071.1 2151.94  5129.8 2152.59  5143.8 2153.15
  5160.6 2154.44  5166.2 2154.34  5205.3  2157.1  5227.6 2157.82  5241.6 2158.92
  5255.6 2159.52    5264 2160.46  5294.7 2162.48  5308.7 2162.54  5331.1 2163.52
#Mann= 3 ,-1 , 0
  4745.7     .07       0  4990.5     .05       0  4994.5     .07       0
Bank Sta=4990.5,4994.5
XS Rating Curve= 0 ,0
Exp/Cntr=0.3,0.1

Type RM Length L Ch R = 1 ,41262   ,470,470,470
BEGIN DESCRIPTION:
Fessenden Branch 88.0
END DESCRIPTION:
XS GIS Cut Line= 3
      1863974.98     13993725.02        1863675.       13994025.
        1863625.     13994325.02
#Sta/Elev= 30
  4575.5 2167.34  4593.6 2167.23  4603.8 2167.16    4632 2164.98  4681.5 2162.49
  4688.6 2162.42  4724.1 2160.28    4830 2152.93  4872.5 2150.69  4886.6 2150.28
  4957.3 2146.24  5009.9 2146.16    5018 2145.82  5018.3 2145.32  5021.8 2145.32
    5022 2145.82  5027.6 2146.34  5080.8 2147.41  5111.3 2147.58  5131.5 2148.44
  5161.9 2150.63  5182.2 2151.56  5192.4 2151.86  5202.5 2151.68  5210.1 2152.22
  5222.8 2152.48  5232.9 2153.47  5270.9 2155.39  5283.6 2155.41  5303.9 2156.15
#Mann= 5 ,-1 , 0
  4575.5     .07       0  4593.6      .1       0  4724.1     .07       0
    5018     .05       0    5022     .07       0
Bank Sta=5018,5022
XS Rating Curve= 0 ,0
Exp/Cntr=0.3,0.1

Type RM Length L Ch R = 1 ,40792   ,469,469,469
BEGIN DESCRIPTION:
Fessenden Branch 87.0
END DESCRIPTION:
XS GIS Cut Line= 3
      1863475.02     13993624.98        1863325.       13993725.
      1863075.01     13994024.99
#Sta/Elev= 30
  4815.5 2148.88  4864.4 2146.44  4923.7 2143.56  4931.2 2142.73  4937.2 2142.92
  4959.8 2141.27  4967.3 2141.22  4982.3 2138.52  4999.1 2138.39    5003 2140.07
  5009.5  2138.2  5017.3 2140.83  5036.1 2138.01  5036.4 2137.51  5039.9 2137.51
  5040.1 2138.01  5060.2  2138.7  5066.7 2138.28  5073.9  2138.6  5087.6 2139.91
  5095.4 2139.97  5101.9 2141.87  5109.7 2142.57  5116.2  2142.8  5130.5 2142.05
  5159.2 2144.98  5165.7 2144.97  5230.1  2148.6  5308.2 2151.34  5386.3 2156.78
#Mann= 4 ,-1 , 0
  4815.5      .1       0  4864.4     .07       0  5036.1     .05       0
  5040.1     .07       0
Bank Sta=5036.1,5040.1
XS Rating Curve= 0 ,0
Exp/Cntr=0.3,0.1

Type RM Length L Ch R = 1 ,40323   ,432,432,432
BEGIN DESCRIPTION:
Fessenden Branch 86.0
END DESCRIPTION:
XS GIS Cut Line= 3
        1863325.       13993325.        1863025.       13993425.
      1862774.99     13993625.01
#Sta/Elev= 30
  4683.5 2148.44  4746.7 2144.03  4757.3 2143.81  4767.8 2142.45  4820.5 2139.09
  4852.2 2138.34  4862.7 2137.29  4872.3 2137.05  4978.6 2134.06  4995.1 2131.87
  4995.3 2131.37  4998.8 2131.37  4999.1 2131.87  5027.7 2131.89  5035.7 2134.21
  5056.6 2135.44  5063.8 2136.55  5091.8 2137.06  5120.6 2138.44    5135 2139.64
    5199  2141.9  5205.4 2142.74  5213.4 2142.87  5219.8 2143.74  5227.8 2144.06
  5242.2 2145.69  5263.1 2146.97  5277.5 2148.65  5298.3  2149.8  5319.9 2150.26
#Mann= 4 ,-1 , 0
  4683.5      .1       0  4872.3     .07       0  4995.1     .05       0
  4999.1     .07       0
Bank Sta=4995.1,4999.1
XS Rating Curve= 0 ,0
Exp/Cntr=0.3,0.1

Type RM Length L Ch R = 1 ,39891   ,455,455,455
BEGIN DESCRIPTION:
Fessenden Branch 85.0
END DESCRIPTION:
XS GIS Cut Line= 3
      1863124.95       13993025.        1862925.       13993025.
        1862725.       13993225.
#Sta/Elev= 30
  4795.5 2140.11    4798 2140.11  4815.5 2139.28    4826 2138.58  4845.5 2136.88
  4865.5 2135.49  4885.5 2134.83  4895.5 2134.78  4925.5 2133.21  4935.5 2132.57
  4945.5 2131.64  4955.5 2131.26  4965.5 2129.93  4975.5 2128.35  4985.5  2128.2
  4994.6 2127.81  5021.7  2127.3    5022  2126.8  5025.5  2126.8  5025.7  2127.3
  5037.9 2127.73    5052 2129.52  5080.3 2130.62  5094.4 2130.53  5108.6 2130.95
    5151 2133.36  5179.3 2133.84  5235.9 2136.62  5242.9 2136.51  5278.3 2137.29
#Mann= 5 ,-1 , 0
  4795.5     .07       0    4826      .1       0  4994.6     .07       0
  5021.7     .05       0  5025.7     .07       0
Bank Sta=5021.7,5025.7
XS Rating Curve= 0 ,0
Exp/Cntr=0.3,0.1

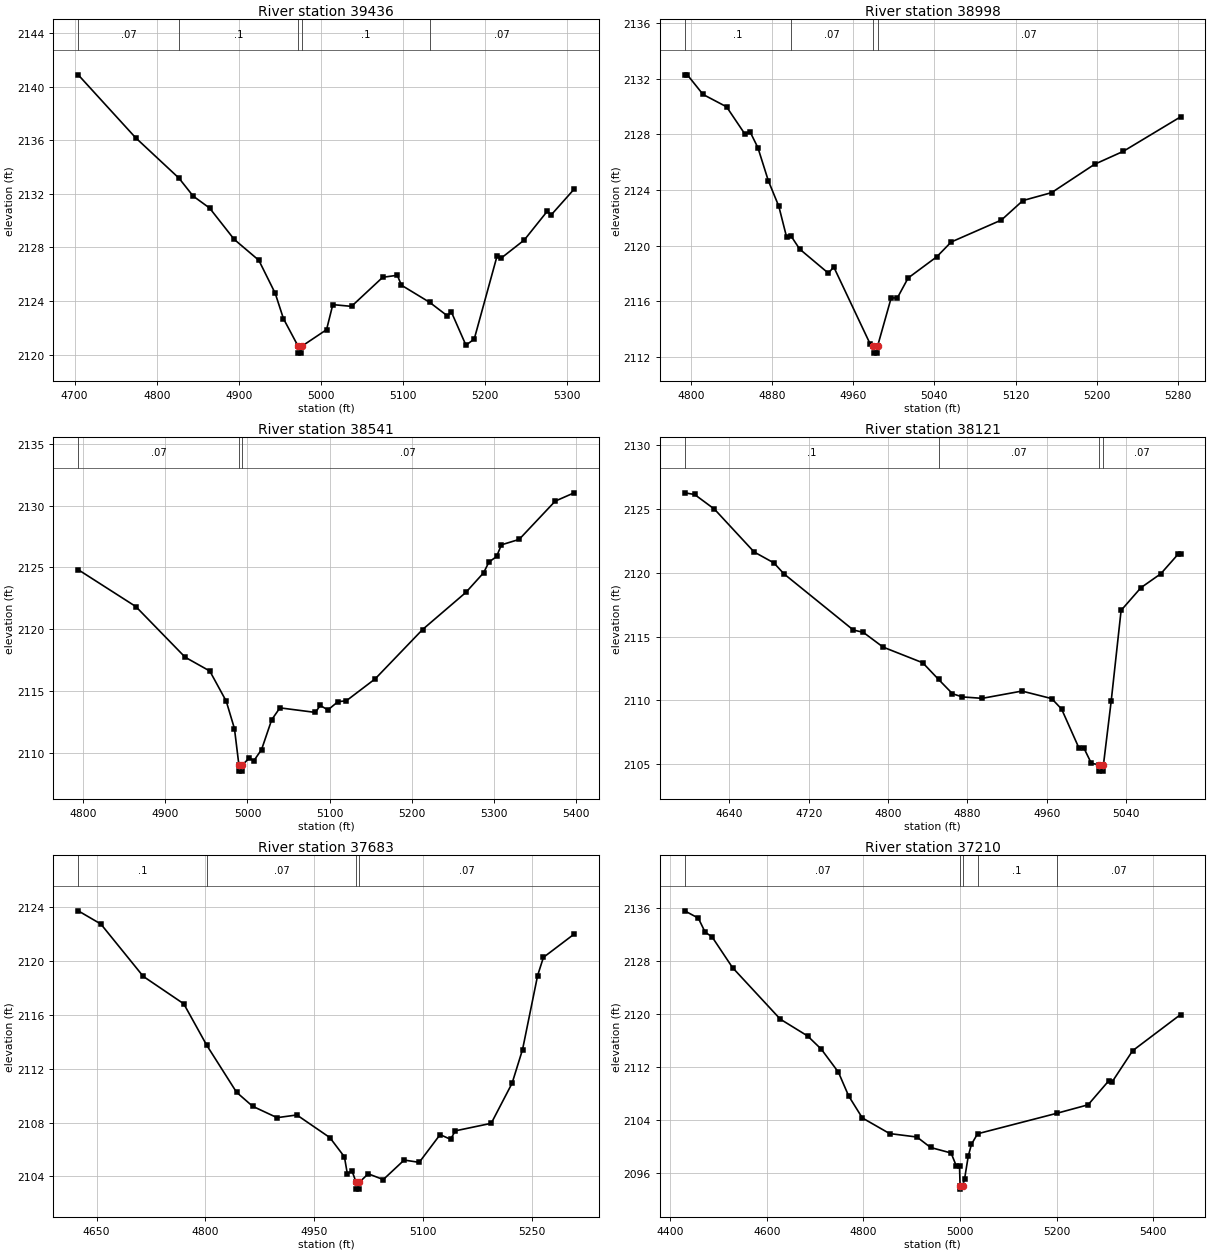
Type RM Length L Ch R = 1 ,39436   ,438,438,438
BEGIN DESCRIPTION:
Fessenden Branch 84.0
END DESCRIPTION:
XS GIS Cut Line= 3
      1863074.96       13992625.        1862775.       13992625.
        1862475.       13992575.
#Sta/Elev= 30
  4704.4 2140.88  4774.4 2136.18  4827.1 2133.17  4844.4 2131.83  4864.4 2130.94
  4894.4  2128.6  4924.4 2127.04  4944.4 2124.57  4954.4 2122.68  4972.4 2120.61
  4972.6 2120.11  4976.1 2120.11  4976.4 2120.61  5006.9 2121.86  5014.5 2123.73
  5037.3  2123.6  5075.3 2125.77  5093.1 2125.92  5098.1 2125.18  5132.5  2123.9
  5153.9  2122.9    5159 2123.17  5176.7  2120.7  5186.8 2121.16  5214.7 2127.38
  5219.8 2127.21  5247.7 2128.55  5275.5 2130.68  5280.6 2130.43  5308.5 2132.35
#Mann= 5 ,-1 , 0
  4704.4     .07       0  4827.1      .1       0  4972.4     .05       0
  4976.4      .1       0  5132.5     .07       0
Bank Sta=4972.4,4976.4
XS Rating Curve= 0 ,0
Exp/Cntr=0.3,0.1

Type RM Length L Ch R = 1 ,38998   ,457,457,457
BEGIN DESCRIPTION:
Fessenden Branch 83.0
END DESCRIPTION:
XS GIS Cut Line= 3
      1862875.03     13992174.99        1862675.       13992225.
      1862475.02     13992424.98
#Sta/Elev= 30
  4793.8 2132.29  4796.4 2132.29  4811.9 2130.88  4835.1 2129.99  4853.1 2128.04
  4858.3 2128.19    4866 2127.05  4876.3 2124.67  4886.6 2122.84  4894.3 2120.62
  4898.4 2120.73  4907.2 2119.76  4935.6 2118.02  4940.7 2118.49  4976.8 2112.92
  4979.8 2112.78  4980.1 2112.28  4983.7 2112.28    4984 2112.78  4997.4 2116.25
  5003.5 2116.25  5014.1 2117.68  5042.4 2119.21  5056.6 2120.27  5106.1 2121.85
  5127.3 2123.25  5155.6 2123.82    5198 2125.86  5226.3 2126.79  5282.8 2129.27
#Mann= 4 ,-1 , 0
  4793.8      .1       0  4898.4     .07       0  4979.8     .05       0
    4984     .07       0
Bank Sta=4979.8,4984
XS Rating Curve= 0 ,0
Exp/Cntr=0.3,0.1

Type RM Length L Ch R = 1 ,38541   ,420,420,420
BEGIN DESCRIPTION:
Fessenden Branch 82.0
END DESCRIPTION:
XS GIS Cut Line= 3
      1862724.99       13991825.        1862525.       13991825.
        1862175.       13992025.
#Sta/Elev= 30
  4794.2 2124.82  4864.2 2121.84  4924.2 2117.74  4954.2 2116.62  4974.2 2114.18
  4984.2 2111.96  4989.6 2109.02  4989.8 2108.52  4993.5 2108.52  4993.8 2109.02
  5002.1 2109.57  5007.9 2109.37  5017.2 2110.27  5029.5 2112.68  5039.5 2113.64
  5082.7 2113.27  5088.5 2113.84  5097.8 2113.47  5110.1 2114.14  5120.2 2114.21
  5155.4 2115.99    5213 2119.98  5265.6 2122.98  5287.2 2124.57  5293.6 2125.43
    5303 2125.89  5308.8 2126.83  5330.4 2127.27  5374.3 2130.37  5397.3 2131.04
#Mann= 3 ,-1 , 0
  4794.2     .07       0  4989.6     .05       0  4993.8     .07       0
Bank Sta=4989.6,4993.8
XS Rating Curve= 0 ,0
Exp/Cntr=0.3,0.1

Type RM Length L Ch R = 1 ,38121   ,438,438,438
BEGIN DESCRIPTION:
Fessenden Branch 81.0
END DESCRIPTION:
XS GIS Cut Line= 3
      1862675.02       13991525.        1862275.       13991525.
      1862175.02       13991525.
#Sta/Elev= 30
  4594.9 2126.27  4604.9 2126.14  4624.9 2124.99  4664.9 2121.63  4684.9 2120.77
  4694.9 2119.92  4764.9 2115.51  4774.9 2115.33  4794.9 2114.17  4834.9 2112.94
  4850.9 2111.63  4864.9 2110.51  4874.9 2110.26  4894.9 2110.15  4934.9 2110.72
  4964.9 2110.13  4974.9 2109.31  4992.4 2106.25  4997.4 2106.25  5004.9 2105.05
  5012.8 2104.94  5013.1 2104.44  5016.8 2104.44  5017.1 2104.94  5024.9 2109.93
  5034.9 2117.05  5054.9 2118.83  5074.9 2119.92  5092.4 2121.46  5094.9 2121.46
#Mann= 4 ,-1 , 0
  4594.9      .1       0  4850.9     .07       0  5012.8     .05       0
  5017.1     .07       0
Bank Sta=5012.8,5017.1
XS Rating Curve= 0 ,0
Exp/Cntr=0.3,0.1

Type RM Length L Ch R = 1 ,37683   ,473,473,473
BEGIN DESCRIPTION:
Fessenden Branch 80.0
END DESCRIPTION:
XS GIS Cut Line= 3
      1862674.98     13991224.99        1862325.       13991125.
      1862075.03     13991324.98
#Sta/Elev= 30
  4624.6 2123.73  4655.8 2122.75  4714.3 2118.86  4770.2 2116.82  4801.9 2113.74
    4843 2110.25  4865.1 2109.21  4898.9 2108.36  4926.2 2108.56  4971.7 2106.88
  4991.8 2105.45  4995.8  2104.2  5002.2 2104.41    5008 2103.55  5008.3 2103.05
    5012 2103.05  5012.3 2103.55  5024.6 2104.19  5045.4 2103.76  5074.2 2105.21
    5095 2105.04  5123.8  2107.1  5138.3 2106.75  5144.7 2107.38  5194.3 2107.94
  5223.1 2110.92  5237.5 2113.42  5258.3 2118.92  5266.3 2120.27  5308.7    2122
#Mann= 4 ,-1 , 0
  4624.6      .1       0  4801.9     .07       0    5008     .05       0
  5012.3     .07       0
Bank Sta=5008,5012.3
XS Rating Curve= 0 ,0
Exp/Cntr=0.3,0.1

Type RM Length L Ch R = 1 ,37210   ,468,468,468
BEGIN DESCRIPTION:
Fessenden Branch 79.0
END DESCRIPTION:
XS GIS Cut Line= 3
      1862674.97     13990275.03        1862275.       13990675.
      1861925.02     13990974.99
#Sta/Elev= 30
    4430 2135.57  4458.2 2134.47  4472.4 2132.34  4486.5 2131.66    4529 2127.01
  4627.9 2119.23  4684.5 2116.69  4712.8  2114.7  4748.2 2111.23  4769.4 2107.65
  4797.7 2104.33  4854.2 2101.97  4910.8 2101.45  4939.1 2099.87  4981.5 2099.04
  4992.1 2097.11  4998.9 2097.11  5000.1 2094.09  5000.5 2093.59  5005.4 2094.09
  5009.4 2095.13    5017 2098.56  5023.6 2100.35  5036.3 2101.94  5200.3 2105.03
  5265.1 2106.31  5307.9 2109.94  5314.5 2109.73  5357.3 2114.47  5456.6 2119.93
#Mann= 5 ,-1 , 0
    4430     .07       0  5000.1     .05       0  5005.4     .07       0
  5036.3      .1       0  5200.3     .07       0
Bank Sta=5000.1,5005.4
XS Rating Curve= 0 ,0
Exp/Cntr=0.3,0.1

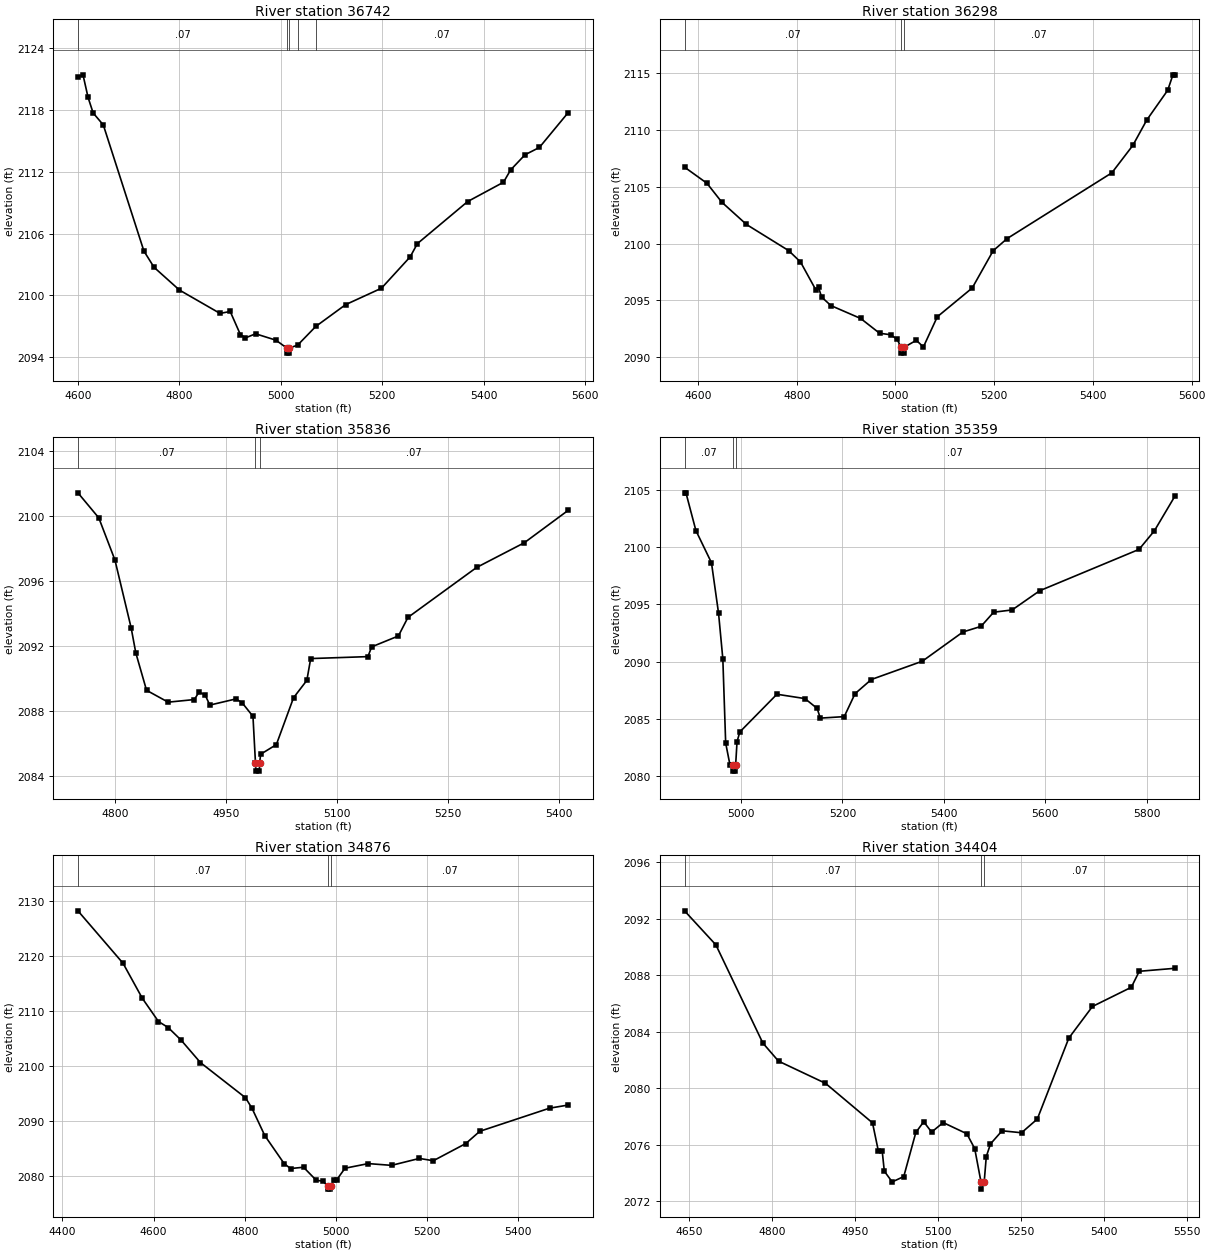
Type RM Length L Ch R = 1 ,36742   ,444,444,444
BEGIN DESCRIPTION:
Fessenden Branch 78.0
END DESCRIPTION:
XS GIS Cut Line= 3
      1862474.99       13990275.        1862075.       13990275.
      1861674.98     13990675.02
#Sta/Elev= 30
  4600.4 2121.24  4610.4 2121.43  4620.4 2119.23  4630.4 2117.72  4650.4 2116.56
  4730.4  2104.3  4750.4 2102.72  4800.4 2100.51  4880.4 2098.24  4900.4 2098.43
  4920.4 2096.19  4930.4 2095.86  4950.4 2096.26  4990.4 2095.64  5011.8 2094.88
  5012.3 2094.38  5016.8 2094.38  5017.2 2094.88  5033.3 2095.16  5068.9 2096.97
  5127.7 2099.09  5198.4 2100.69    5255 2103.74  5269.1 2105.02  5368.1 2109.11
  5438.8 2110.99  5452.9 2112.19  5481.2 2113.66  5509.5 2114.37  5566.1 2117.75
#Mann= 5 ,-1 , 0
  4600.4     .07       0  5011.8     .05       0  5017.2     .07       0
  5033.3      .1       0  5068.9     .07       0
Bank Sta=5011.8,5017.2
XS Rating Curve= 0 ,0
Exp/Cntr=0.3,0.1

Type RM Length L Ch R = 1 ,36298   ,462,462,462
BEGIN DESCRIPTION:
Fessenden Branch 77.0
END DESCRIPTION:
XS GIS Cut Line= 3
      1862224.99       13989775.        1861825.       13989925.
      1861424.98     13990325.02
#Sta/Elev= 30
  4572.8 2106.74  4618.2 2105.32  4648.4 2103.65  4698.3 2101.69  4783.7 2099.39
  4807.7 2098.39  4838.9 2095.92  4844.2 2096.14  4850.5  2095.3  4869.2 2094.55
  4929.7 2093.41  4967.9 2092.11  4990.2 2091.98  5003.5 2091.58  5011.4 2090.86
  5011.8 2090.36  5016.4 2090.36  5016.9 2090.86  5042.4 2091.49  5056.6  2090.9
  5084.8 2093.56  5155.6  2096.1    5198 2099.38  5226.3 2100.45  5438.4 2106.24
  5480.8 2108.65  5509.1 2110.89  5551.5 2113.51  5562.1 2114.87  5565.7 2114.87
#Mann= 3 ,-1 , 0
  4572.8     .07       0  5011.4     .05       0  5016.9     .07       0
Bank Sta=5011.4,5016.9
XS Rating Curve= 0 ,0
Exp/Cntr=0.3,0.1

Type RM Length L Ch R = 1 ,35836   ,477,477,477
BEGIN DESCRIPTION:
Fessenden Branch 76.0
END DESCRIPTION:
XS GIS Cut Line= 3
      1861725.02     13989374.98        1861575.       13989575.
      1861475.01     13989974.96
#Sta/Elev= 30
    4750 2101.42  4778.2 2099.88    4800 2097.29  4821.9 2093.12  4828.2 2091.58
  4842.7 2089.28  4871.9 2088.55  4907.3 2088.71  4913.6 2089.17  4921.9 2088.99
  4928.2 2088.37  4963.6 2088.75  4971.9 2088.51  4986.5 2087.68  4989.9 2084.81
  4990.4 2084.31  4995.1 2084.31  4995.5 2084.81  4996.9 2085.35  5018.1 2085.94
  5041.3 2088.82  5059.3 2089.89  5064.5 2091.23  5141.8 2091.35  5146.9 2091.95
    5183 2092.62  5195.9 2093.76  5288.6 2096.83  5353.1 2098.35  5412.3 2100.34
#Mann= 3 ,-1 , 0
    4750     .07       0  4989.9     .05       0  4995.5     .07       0
Bank Sta=4989.9,4995.5
XS Rating Curve= 0 ,0
Exp/Cntr=0.3,0.1

Type RM Length L Ch R = 1 ,35359   ,483,483,483
BEGIN DESCRIPTION:
Fessenden Branch 75.0
END DESCRIPTION:
XS GIS Cut Line= 3
      1861425.01     13989074.97        1861375.       13989175.
      1861075.01     13989974.97
#Sta/Elev= 30
  4888.7 2104.77  4891.5 2104.77  4911.1 2101.47  4941.8 2098.65  4955.8 2094.22
  4964.2 2090.24  4969.8 2082.87  4978.2 2080.97  4983.8 2080.91  4984.2 2080.41
  4988.9 2080.41  4989.4 2080.91  4992.2 2082.99  4997.7 2083.84  5070.8 2087.14
    5126 2086.76  5150.1  2085.9  5156.3 2085.05  5203.5 2085.18  5224.8 2087.19
  5256.9 2088.43  5357.4 2090.03  5437.5 2092.59  5473.1 2093.08    5498 2094.32
  5534.5 2094.52  5588.8  2096.2  5784.6 2099.82  5814.9 2101.45  5854.9 2104.45
#Mann= 3 ,-1 , 0
  4888.7     .07       0  4983.8     .05       0  4989.4     .07       0
Bank Sta=4983.8,4989.4
XS Rating Curve= 0 ,0
Exp/Cntr=0.3,0.1

Type RM Length L Ch R = 1 ,34876   ,472,472,472
BEGIN DESCRIPTION:
Fessenden Branch 74.0
END DESCRIPTION:
XS GIS Cut Line= 3
        1861325.       13988675.        1860925.       13989075.
        1861025.     13989575.01
#Sta/Elev= 30
  4433.9 2128.21  4532.9 2118.68  4575.3  2112.3  4610.7 2108.09  4631.9    2107
  4660.2 2104.72  4702.6 2100.64  4801.6 2094.24  4815.7 2092.35    4844 2087.35
  4886.5 2082.26  4900.6 2081.37  4928.9 2081.61  4957.2 2079.21  4971.3  2079.1
  4982.6 2078.13  4983.1 2077.63  4987.8 2077.63  4988.2 2078.13  4996.1 2079.37
  5002.1 2079.37    5020 2081.43    5071 2082.27    5122 2081.95  5183.2 2083.21
  5213.7 2082.79  5285.1 2085.92  5315.7 2088.14  5468.7 2092.34  5509.5 2092.91
#Mann= 3 ,-1 , 0
  4433.9     .07       0  4982.6     .05       0  4988.2     .07       0
Bank Sta=4982.6,4988.2
XS Rating Curve= 0 ,0
Exp/Cntr=0.3,0.1

Type RM Length L Ch R = 1 ,34404   ,453,453,453
BEGIN DESCRIPTION:
Fessenden Branch 73.0
END DESCRIPTION:
XS GIS Cut Line= 3
      1860774.99     13988625.01        1860525.       13988875.
      1860175.03     13989274.96
#Sta/Elev= 30
  4642.3 2092.57  4698.9 2090.16  4783.7 2083.21    4812 2081.93  4896.8 2080.36
  4981.7 2077.56  4992.3 2075.56  4999.2 2075.56    5003 2074.14  5017.2 2073.38
  5038.1 2073.76  5059.9 2076.88  5074.1 2077.64  5088.4 2076.91  5109.3 2077.58
    5152 2076.79  5166.2 2075.74  5177.6 2073.37    5178 2072.87  5183.3 2073.37
  5187.1 2075.17  5194.7 2076.07  5215.6    2077  5250.7 2076.86  5279.2 2077.83
  5336.1 2083.56  5378.8  2085.8    5449 2087.16  5463.3 2088.29  5527.3  2088.5
#Mann= 3 ,-1 , 0
  4642.3     .07       0  5177.6     .05       0  5183.3     .07       0
Bank Sta=5177.6,5183.3
XS Rating Curve= 0 ,0
Exp/Cntr=0.3,0.1

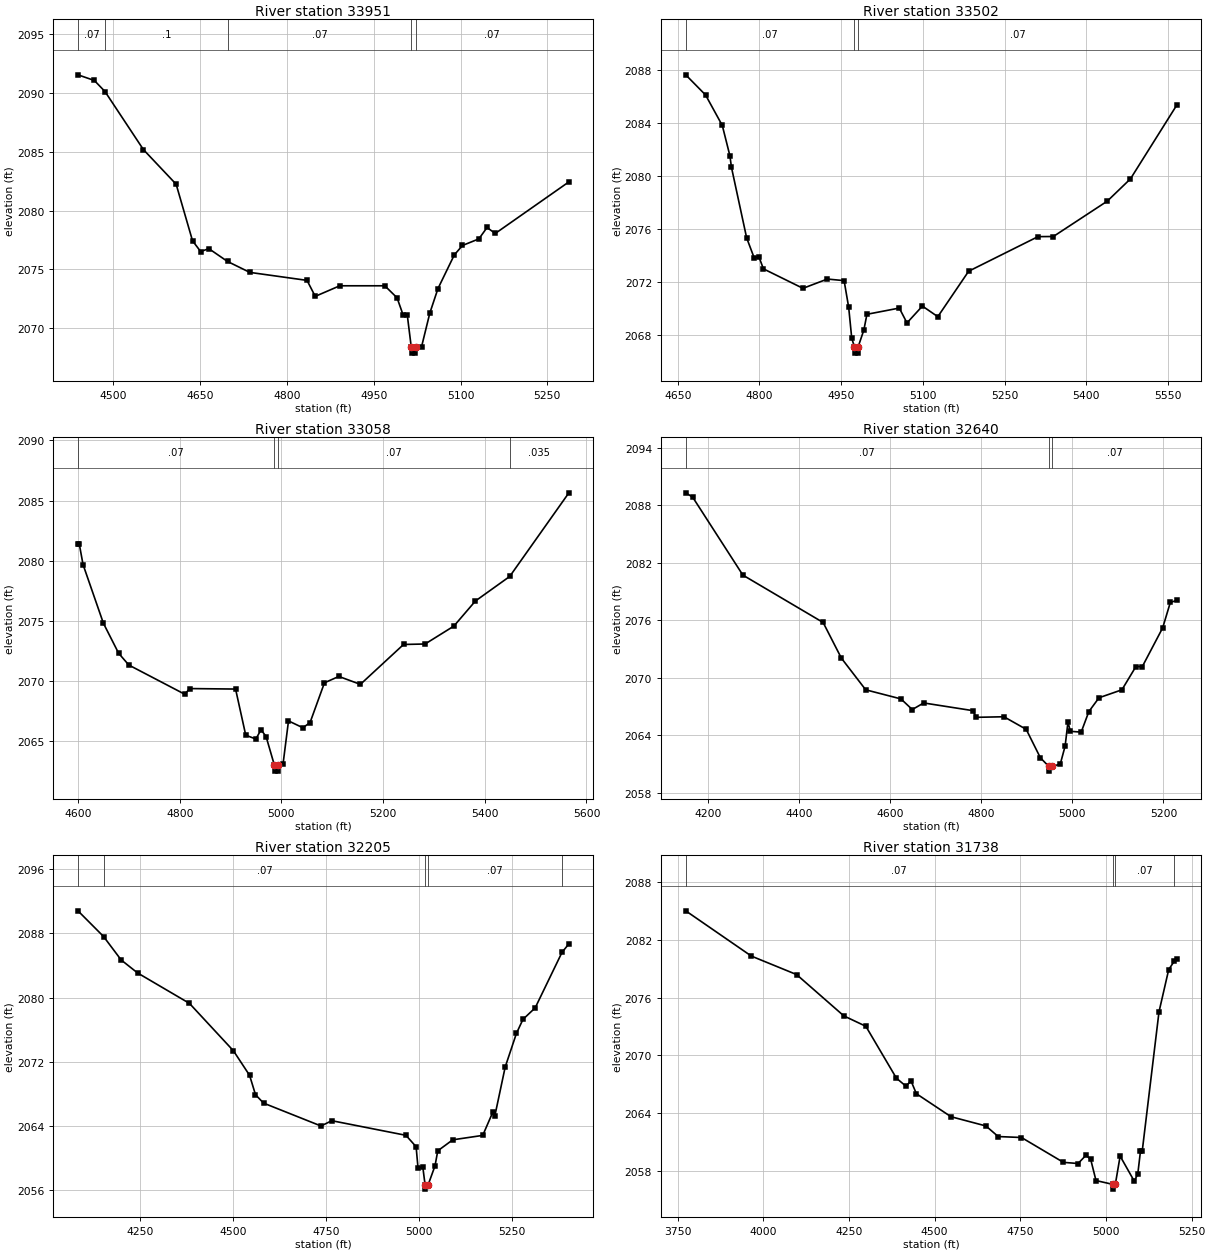
Type RM Length L Ch R = 1 ,33951   ,449,449,449
BEGIN DESCRIPTION:
Fessenden Branch 72.0
END DESCRIPTION:
XS GIS Cut Line= 3
      1860524.98     13988325.02        1860125.       13988725.
        1859925.       13988925.
#Sta/Elev= 30
  4438.7 2091.56    4467 2091.08  4485.4 2090.14  4551.8  2085.2  4608.4 2082.25
  4636.7 2077.44  4650.8 2076.52  4664.9 2076.77  4697.2 2075.68  4735.7 2074.75
  4834.6 2074.07  4848.8 2072.71  4891.2 2073.61    4969 2073.61  4990.2 2072.59
  5000.8 2071.11  5007.9 2071.11  5014.8 2068.38  5015.3 2067.88  5021.6 2067.88
  5022.1 2068.38  5032.6 2068.43  5046.8 2071.28  5060.9 2073.37  5089.2 2076.24
  5103.3 2077.04  5131.6  2077.6  5145.8 2078.57  5159.9 2078.06  5287.2 2082.45
#Mann= 5 ,-1 , 0
  4438.7     .07       0  4485.4      .1       0  4697.2     .07       0
  5014.8     .05       0  5022.1     .07       0
Bank Sta=5014.8,5022.1
XS Rating Curve= 0 ,0
Exp/Cntr=0.3,0.1

Type RM Length L Ch R = 1 ,33502   ,444,444,444
BEGIN DESCRIPTION:
Fessenden Branch 71.0
END DESCRIPTION:
XS GIS Cut Line= 3
      1860375.02     13988174.99        1860075.       13988325.
      1859675.01     13988724.99
#Sta/Elev= 30
  4664.6 2087.65    4701 2086.13  4731.7 2083.83  4745.7 2081.54  4748.5 2080.68
  4776.4 2075.35  4790.4 2073.82  4798.8 2073.93  4807.2 2073.01  4879.8 2071.54
  4924.6 2072.24  4955.3 2072.12  4963.7 2070.11  4969.3 2067.78    4974 2067.15
  4974.5 2066.65  4980.8 2066.65  4981.3 2067.15  4991.6  2068.4  4997.2 2069.58
  5056.6 2070.05  5070.7 2068.93    5099  2070.2  5127.3  2069.4  5183.9 2072.83
  5311.2 2075.44  5339.4 2075.45  5438.4 2078.12  5480.9  2079.8  5565.7 2085.35
#Mann= 3 ,-1 , 0
  4664.6     .07       0    4974     .05       0  4981.3     .07       0
Bank Sta=4974,4981.3
XS Rating Curve= 0 ,0
Exp/Cntr=0.3,0.1

Type RM Length L Ch R = 1 ,33058   ,418,418,418
BEGIN DESCRIPTION:
Fessenden Branch 70.0
END DESCRIPTION:
XS GIS Cut Line= 3
      1860224.95       13987975.        1859825.       13987975.
      1859425.03     13988374.97
#Sta/Elev= 30
  4599.8  2081.4  4602.3  2081.4  4609.8 2079.67  4649.8 2074.79  4679.8 2072.29
  4699.8 2071.31  4809.8 2068.88  4819.8 2069.35  4909.8 2069.31  4929.8 2065.47
  4949.8 2065.15  4959.8 2065.93  4969.8 2065.36  4986.1 2062.98  4986.6 2062.48
    4993 2062.48  4993.5 2062.98  5003.3 2063.11  5013.9 2066.66  5042.2 2066.09
  5056.3 2066.52  5084.6 2069.83  5112.9 2070.36  5155.3  2069.7  5240.2 2073.02
  5282.6 2073.06  5339.2 2074.55  5381.6 2076.64    5449 2078.68  5565.4 2085.64
#Mann= 4 ,-1 , 0
  4599.8     .07       0  4986.1     .05       0  4993.5     .07       0
    5449    .035       0
Bank Sta=4986.1,4993.5
XS Rating Curve= 0 ,0
Exp/Cntr=0.3,0.1

Type RM Length L Ch R = 1 ,32640   ,435,435,435
BEGIN DESCRIPTION:
Fessenden Branch 69.0
END DESCRIPTION:
XS GIS Cut Line= 3
      1860425.02     13987925.01        1859625.       13987625.
      1859425.03     13987525.01
#Sta/Elev= 30
  4151.1 2089.28  4166.3 2088.83  4276.6  2080.7  4452.8 2075.76  4492.9 2072.04
  4546.3 2068.74  4623.7 2067.79  4648.6 2066.68  4673.6 2067.37  4781.2 2066.57
  4789.3 2065.87  4849.8 2065.93  4898.7 2064.62  4929.9 2061.65  4948.2 2060.76
  4948.7 2060.26  4956.1 2060.76  4973.5 2060.99  4984.2 2062.87  4990.4 2065.37
  4995.7 2064.41  5019.5 2064.33  5036.3 2066.47  5058.6 2067.91  5108.9 2068.74
  5139.7 2071.17  5153.7 2071.16  5198.4  2075.2  5215.2 2077.85  5229.1 2078.06
#Mann= 3 ,-1 , 0
  4151.1     .07       0  4948.2     .05       0  4956.1     .07       0
Bank Sta=4948.2,4956.1
XS Rating Curve= 0 ,0
Exp/Cntr=0.3,0.1

Type RM Length L Ch R = 1 ,32205   ,467,467,467
BEGIN DESCRIPTION:
Fessenden Branch 68.0
END DESCRIPTION:
XS GIS Cut Line= 3
      1860524.97     13987674.98        1859725.       13987225.
      1859324.96     13987275.01
#Sta/Elev= 30
  4082.6  2090.8  4151.5  2087.6  4198.9 2084.68  4243.2 2083.06  4382.5 2079.28
    4501 2073.37  4544.4 2070.32  4560.3 2067.91    4582 2066.86  4736.6 2064.01
  4765.6 2064.67  4965.1 2062.85  4992.5 2061.43  4997.6  2058.8  5010.5 2058.92
  5016.7 2056.65  5017.2 2056.15  5024.6 2056.65  5043.3 2059.04  5050.8 2060.92
  5091.1 2062.29  5171.8 2062.84  5199.5  2065.8  5204.5  2065.3  5232.2 2071.35
  5262.5 2075.55  5280.1 2077.29  5312.9 2078.72  5385.1 2085.63  5403.6 2086.69
#Mann= 5 ,-1 , 0
  4082.6      .1       0  4151.5     .07       0  5016.7     .05       0
  5024.6     .07       0  5385.1      .1       0
Bank Sta=5016.7,5024.6
XS Rating Curve= 0 ,0
Exp/Cntr=0.3,0.1

Type RM Length L Ch R = 1 ,31738   ,464,464,464
BEGIN DESCRIPTION:
Fessenden Branch 67.0
END DESCRIPTION:
XS GIS Cut Line= 3
      1860724.94     13987408.33        1859675.       13986775.
      1859475.02     13986725.01
#Sta/Elev= 30
  3773.8 2085.02  3965.3 2080.32  4097.3  2078.4  4235.1 2074.11  4299.3 2073.03
  4388.5 2067.64    4416 2066.82  4431.2 2067.35  4446.7 2066.03  4547.7 2063.64
  4649.6 2062.68  4685.5 2061.58  4753.4 2061.48  4875.7  2058.9  4918.5 2058.78
  4941.6 2059.64  4955.3 2059.21  4970.8 2057.01  5019.2 2056.62  5019.7 2056.12
  5027.2 2056.62  5041.2 2059.55  5082.4 2056.95  5092.7 2057.69  5100.5 2060.05
  5105.6 2060.05  5154.6 2074.53  5182.9 2078.92  5199.8 2079.82  5206.1 2080.05
#Mann= 4 ,-1 , 0
  3773.8     .07       0  5019.2     .05       0  5027.2     .07       0
  5199.8      .1       0
Bank Sta=5019.2,5027.2
XS Rating Curve= 0 ,0
Exp/Cntr=0.3,0.1