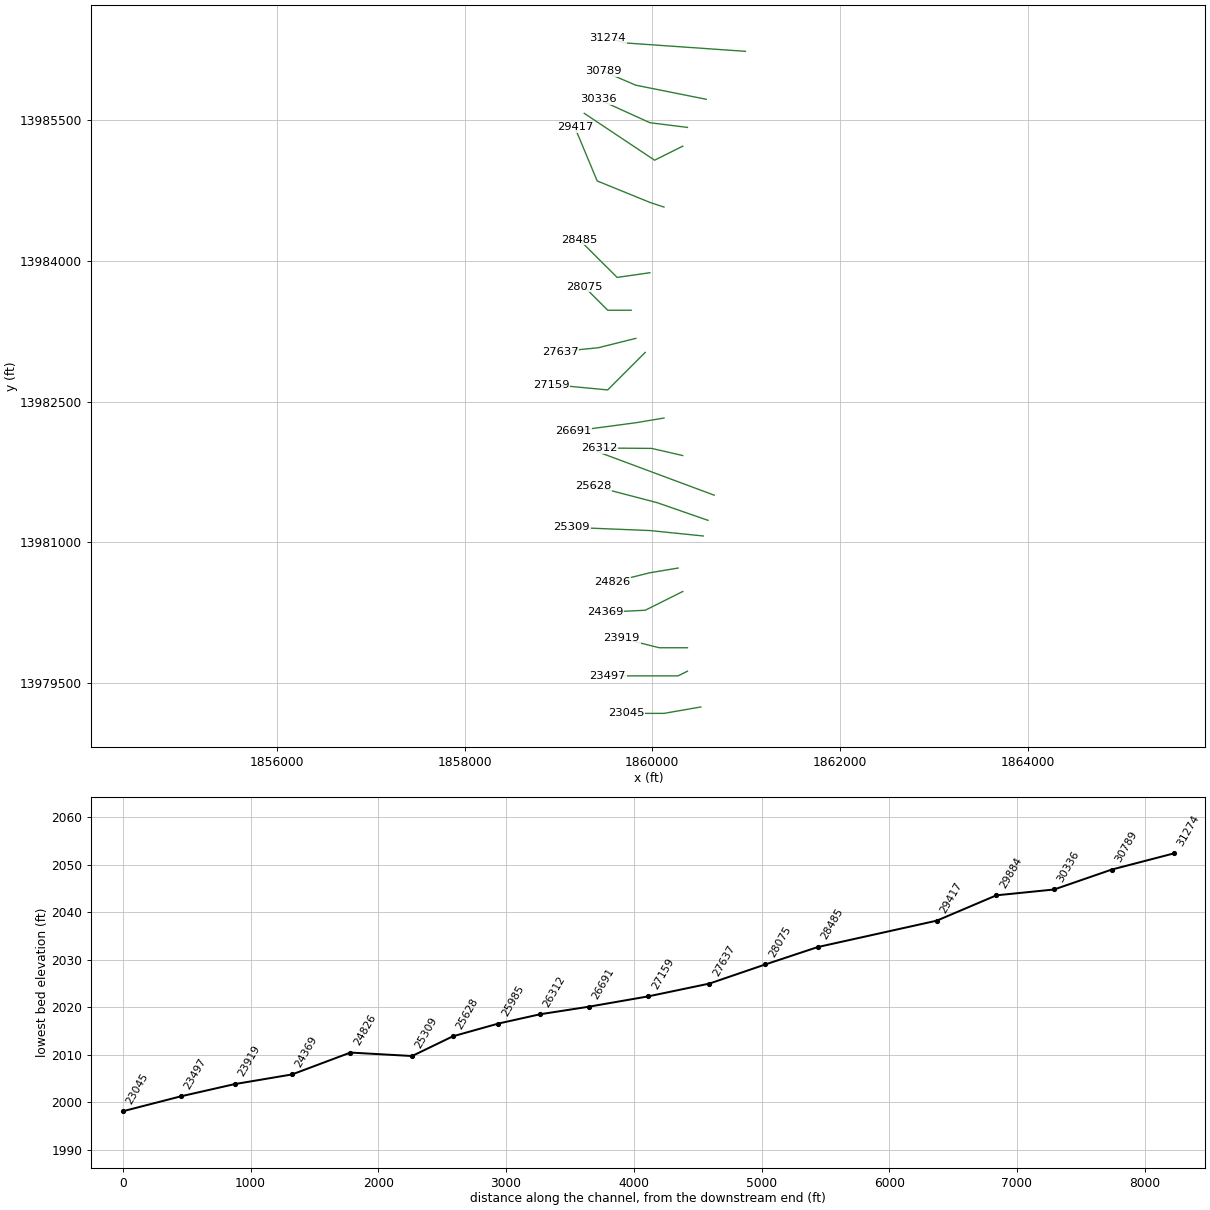
HEC-RAS study Fessenden Branch.prj: Fessenden Branch Base Level Engineering

--- Fessenden Branch.g01 (geometry) --- (continued)

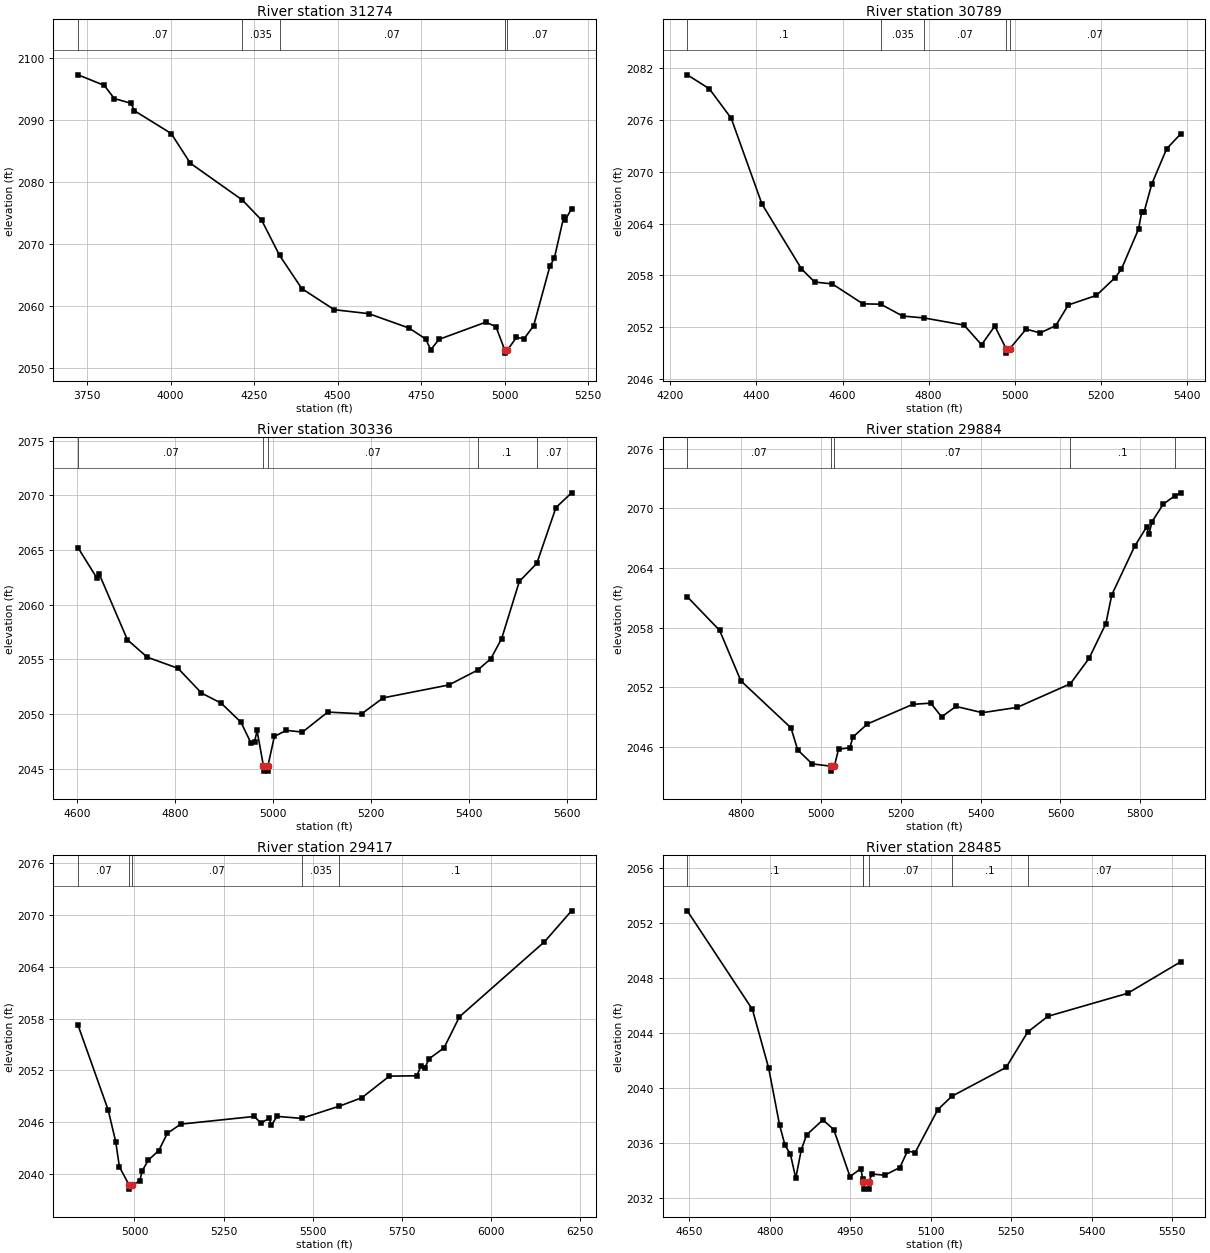
Type RM Length L Ch R = 1 ,31274   ,485,485,485
BEGIN DESCRIPTION:
Fessenden Branch 66.0
END DESCRIPTION:
XS GIS Cut Line= 3
      1860993.23     13986236.46        1859725.       13986325.
      1859524.97     13986375.01
#Sta/Elev= 30
  3723.2 2097.36  3801.6 2095.65  3831.7 2093.52  3881.8 2092.76  3891.8 2091.56
  4002.1 2087.87  4059.2 2083.08  4214.9 2077.13  4272.8 2073.87  4326.5 2068.18
  4393.1 2062.81  4490.1  2059.4  4593.5 2058.76  4713.8 2056.44    4764 2054.67
  4779.1 2052.93  4804.1 2054.61  4944.4 2057.39  4974.5 2056.64  5000.8 2052.88
  5001.3 2052.38  5008.8 2052.88  5035.7 2054.92  5058.9 2054.73  5087.3 2056.81
  5136.2 2066.49  5149.1 2067.69  5177.5 2074.43  5182.6 2073.97  5200.7 2075.73
#Mann= 5 ,-1 , 0
  3723.2     .07       0  4214.9    .035       0  4326.5     .07       0
  5000.8     .05       0  5008.8     .07       0
Bank Sta=5000.8,5008.8
XS Rating Curve= 0 ,0
Exp/Cntr=0.3,0.1

Type RM Length L Ch R = 1 ,30789   ,453,453,453
BEGIN DESCRIPTION:
Fessenden Branch 65.0
END DESCRIPTION:
XS GIS Cut Line= 3
      1860574.97     13985725.01        1859825.       13985875.
      1859475.01       13986025.
#Sta/Elev= 30
  4239.6 2081.24  4290.6 2079.63  4341.5 2076.21  4412.9 2066.27  4504.7 2058.75
  4535.3 2057.23  4576.1 2057.01  4647.5  2054.7  4688.8 2054.66  4739.3 2053.29
    4790 2053.06    4882 2052.24  4922.8 2049.96  4953.4 2052.12    4980 2049.49
  4980.5 2048.99  4988.1 2049.49  5026.2 2051.77  5058.8 2051.33  5095.1 2052.18
  5124.1 2054.57  5189.4 2055.68  5232.9 2057.74  5247.4 2058.72  5287.3 2063.37
  5294.5 2065.34    5300 2065.33  5318.1 2068.61  5352.6 2072.68  5385.2  2074.4
#Mann= 5 ,-1 , 0
  4239.6      .1       0  4688.8    .035       0    4790     .07       0
    4980     .05       0  4988.1     .07       0
Bank Sta=4980,4988.1
XS Rating Curve= 0 ,0
Exp/Cntr=0.3,0.1

Type RM Length L Ch R = 1 ,30336   ,452,452,452
BEGIN DESCRIPTION:
Fessenden Branch 64.0
END DESCRIPTION:
XS GIS Cut Line= 3
      1860374.96       13985425.        1859975.       13985475.
      1859425.03     13985724.99
#Sta/Elev= 30
  4601.6  2065.2  4639.4 2062.48  4644.4 2062.84  4702.3 2056.79  4742.7  2055.2
  4805.6 2054.18  4853.5 2051.92  4893.8 2050.99  4934.1 2049.25  4954.3 2047.37
  4961.8 2047.44  4966.9  2048.5  4979.8 2045.28  4980.3 2044.78  4988.7 2044.78
  4989.2 2045.28  5002.2 2047.95  5026.6 2048.51  5059.6 2048.35  5111.2 2050.18
  5180.4 2050.02  5224.4 2051.48  5358.4 2052.66  5417.2 2054.02  5444.1 2055.06
    5466 2056.88  5502.3 2062.13  5537.9 2063.78    5577 2068.88  5608.8 2070.23
#Mann= 5 ,-1 , 0
  4601.6     .07       0  4979.8     .05       0  4989.2     .07       0
  5417.2      .1       0  5537.9     .07       0
Bank Sta=4979.8,4989.2
XS Rating Curve= 0 ,0
Exp/Cntr=0.3,0.1

Type RM Length L Ch R = 1 ,29884   ,467,467,467
BEGIN DESCRIPTION:
Fessenden Branch 63.0
END DESCRIPTION:
XS GIS Cut Line= 3
      1860324.99       13985225.        1860025.       13985075.
      1859274.99     13985575.01
#Sta/Elev= 30
  4664.6 2061.09  4745.6 2057.71  4798.8 2052.64  4924.5  2047.9  4941.3 2045.68
  4977.6 2044.28  5023.8 2044.05  5024.3 2043.55  5033.2 2044.05  5043.6 2045.75
  5072.1 2045.91  5079.6 2046.97  5115.7 2048.29  5229.9 2050.27  5274.9 2050.39
    5302 2049.01    5338 2050.06  5404.1 2049.43  5491.3 2049.96  5624.7 2052.34
  5671.5 2054.89  5713.6 2058.38  5728.6 2061.29  5785.7 2066.16  5815.8 2068.11
  5821.8 2067.39  5829.3 2068.64  5857.8 2070.42  5886.3 2071.24  5901.4 2071.55
#Mann= 5 ,-1 , 0
  4664.6     .07       0  5023.8     .05       0  5033.2     .07       0
  5624.7      .1       0  5886.3     .07       0
Bank Sta=5023.8,5033.2
XS Rating Curve= 0 ,0
Exp/Cntr=0.3,0.1

Type RM Length L Ch R = 1 ,29417   ,932,932,932
BEGIN DESCRIPTION:
Fessenden Branch 62.0
END DESCRIPTION:
XS GIS Cut Line= 4
      1860124.98     13984575.01        1859975.       13984625.
      1859412.95       13984854.        1859175.     13985425.01
#Sta/Elev= 30
    4842 2057.21  4926.3  2047.4  4947.4 2043.73  4957.9 2040.79  4984.7 2038.71
  4985.2 2038.21  4994.5 2038.71  5014.8 2039.15  5021.7 2040.33  5038.9 2041.57
  5068.3 2042.69  5092.4 2044.69  5129.7 2045.75  5335.8 2046.64  5354.5 2045.89
    5378 2046.41  5383.9  2045.6  5399.6 2046.65  5468.6 2046.42  5574.8 2047.84
  5637.9 2048.82  5714.8 2051.32  5791.7 2051.36  5803.1 2052.45  5813.9 2052.26
  5826.4 2053.34  5868.1  2054.6  5911.4 2058.21  6149.8 2066.91  6225.6  2070.5
#Mann= 5 ,-1 , 0
    4842     .07       0  4984.7     .05       0  4994.5     .07       0
  5468.6    .035       0  5574.8      .1       0
Bank Sta=4984.7,4994.5
XS Rating Curve= 0 ,0
Exp/Cntr=0.3,0.1

Type RM Length L Ch R = 1 ,28485   ,410,410,410
BEGIN DESCRIPTION:
Fessenden Branch 61.0
END DESCRIPTION:
XS GIS Cut Line= 3
      1859975.04     13983875.01        1859625.       13983825.
      1859224.99     13984225.01
#Sta/Elev= 30
  4646.4 2052.86  4767.7  2045.7    4798 2041.44  4818.2 2037.33  4828.3 2035.85
  4838.4  2035.2  4848.5 2033.44  4858.6 2035.49  4868.7 2036.59    4899 2037.68
  4919.2 2036.98  4949.5 2033.56  4969.7 2034.14  4973.3 2033.38  4974.4 2033.15
  4974.9 2032.65  4984.6 2032.65  4985.1 2033.15  4989.9 2033.75  5014.1 2033.66
  5042.4 2034.22  5056.6 2035.42  5070.7  2035.3  5113.1 2038.42  5139.1 2039.39
  5240.4 2041.49  5280.6 2044.06  5318.2  2045.2  5466.7 2046.87  5565.7 2049.16
#Mann= 6 ,-1 , 0
  4646.4      .1       0  4973.3     .07       0  4974.4     .05       0
  4985.1     .07       0  5139.1      .1       0  5280.6     .07       0
Bank Sta=4974.4,4985.1
XS Rating Curve= 0 ,0
Exp/Cntr=0.3,0.1

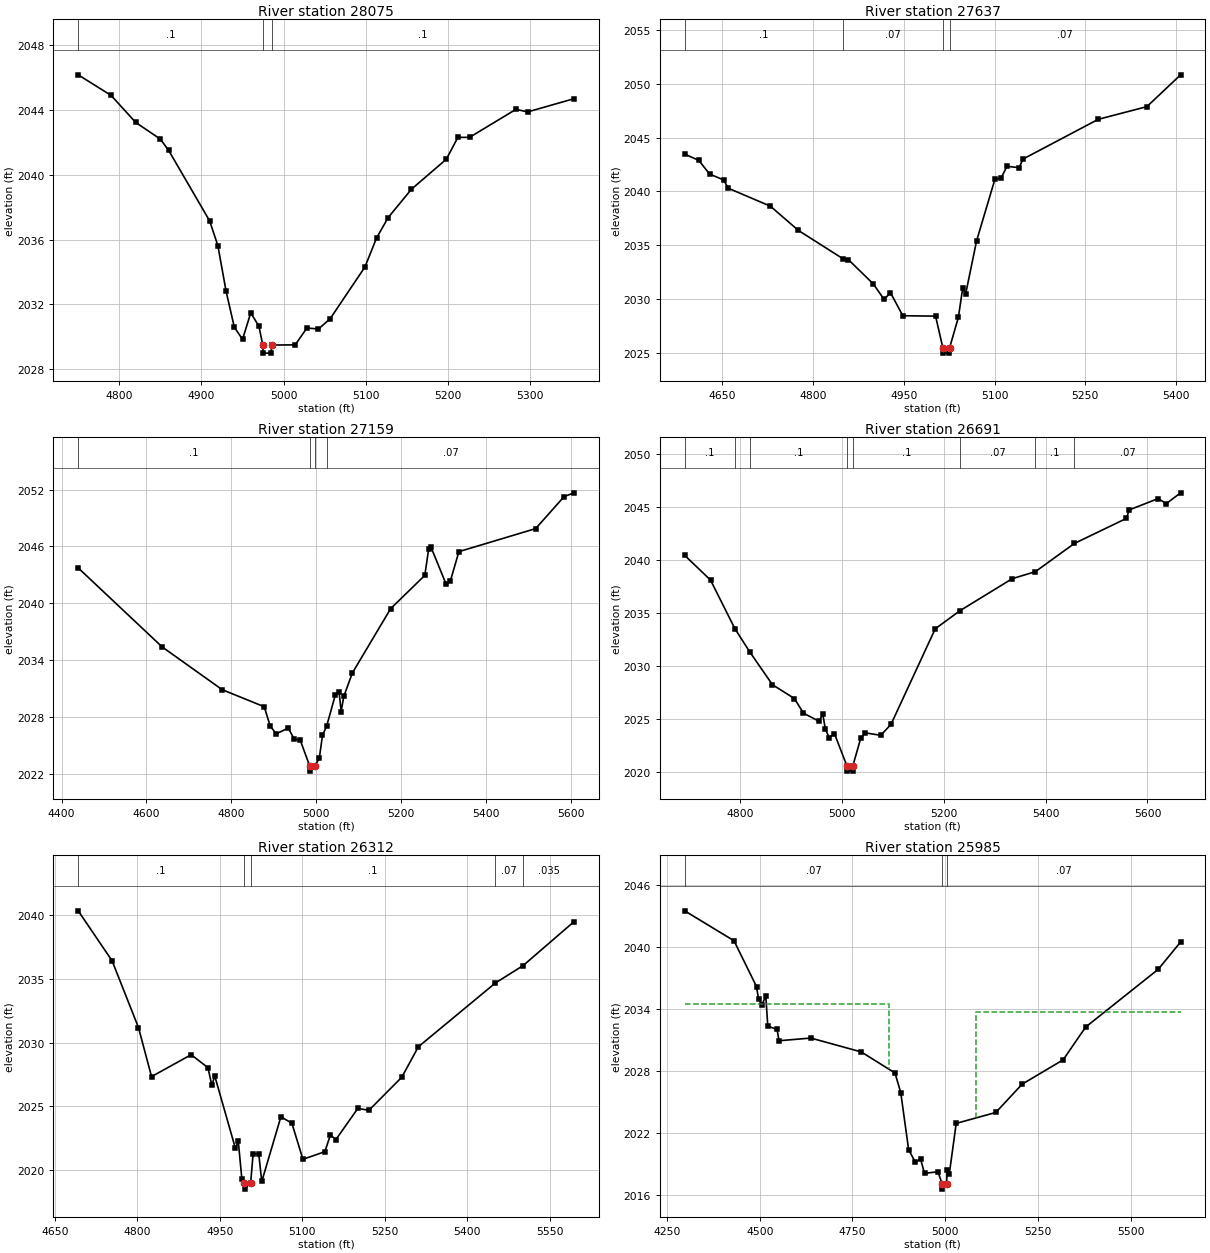
Type RM Length L Ch R = 1 ,28075   ,438,438,438
BEGIN DESCRIPTION:
Fessenden Branch 60.0
END DESCRIPTION:
XS GIS Cut Line= 3
      1859775.01       13983475.        1859525.       13983475.
      1859274.97     13983725.03
#Sta/Elev= 30
  4750.1 2046.17  4790.1  2044.9  4820.1 2043.23  4850.1  2042.2  4860.1 2041.51
  4910.1 2037.15  4920.1 2035.62  4930.1  2032.8  4940.1 2030.59  4950.1 2029.84
  4960.1 2031.48  4970.1 2030.64  4974.7 2029.49  4975.2 2028.99    4985 2028.99
  4985.5 2029.49  5014.2  2029.5  5028.4 2030.54  5042.5 2030.48  5056.7 2031.11
  5099.1 2034.31  5113.2  2036.1  5127.4 2037.36  5155.7 2039.11  5198.1 2040.96
  5212.2 2042.31  5226.4 2042.31  5282.9 2044.04  5297.1 2043.88  5353.7  2044.7
#Mann= 3 ,-1 , 0
  4750.1      .1       0  4974.7     .05       0  4985.5      .1       0
Bank Sta=4974.7,4985.5
XS Rating Curve= 0 ,0
Exp/Cntr=0.3,0.1

Type RM Length L Ch R = 1 ,27637   ,478,478,478
BEGIN DESCRIPTION:
Fessenden Branch 59.0
END DESCRIPTION:
XS GIS Cut Line= 3
      1859824.97     13983174.99        1859425.       13983075.
      1859019.48     13983033.74
#Sta/Elev= 30
  4587.7 2043.47  4610.9  2042.9  4628.9 2041.62  4652.1 2041.07  4659.8  2040.3
  4729.4 2038.63  4775.8 2036.37  4849.1 2033.75  4858.3 2033.66  4899.5  2031.4
  4917.5 2029.95  4927.8 2030.59  4948.4 2028.44  5002.5  2028.4  5014.5 2025.46
    5015 2024.96  5025.2 2024.96  5025.7 2025.46  5040.2 2028.29  5047.3    2031
  5052.3 2030.49  5070.3 2035.41  5100.5 2041.12  5110.6 2041.23  5120.6 2042.34
  5140.7 2042.21  5146.9 2043.01  5271.4 2046.71  5351.8 2047.89  5407.6 2050.85
#Mann= 4 ,-1 , 0
  4587.7      .1       0  4849.1     .07       0  5014.5     .05       0
  5025.7     .07       0
Bank Sta=5014.5,5025.7
XS Rating Curve= 0 ,0
Exp/Cntr=0.3,0.1

Type RM Length L Ch R = 1 ,27159   ,468,468,468
BEGIN DESCRIPTION:
Fessenden Branch 58.0
END DESCRIPTION:
XS GIS Cut Line= 3
      1859924.99     13983024.99        1859525.       13982625.
      1858924.58     13982682.04
#Sta/Elev= 30
  4439.1 2043.73  4637.1 2035.38  4778.5 2030.87  4877.5 2029.07  4891.6 2027.03
  4905.8 2026.21  4934.1 2026.82  4948.2 2025.65  4962.3 2025.55    4985 2022.77
  4985.5 2022.27  4996.3 2022.77  5007.3 2023.64  5014.8 2026.06  5024.4 2026.99
    5045 2030.31  5053.8 2030.66  5058.8 2028.56    5065 2030.16  5085.1 2032.63
  5175.5 2039.43  5255.9 2042.94    5265 2045.71  5270.1 2045.97  5306.1 2042.02
  5316.2 2042.36  5336.3 2045.45  5517.1 2047.88  5584.4 2051.27  5607.9 2051.66
#Mann= 4 ,-1 , 0
  4439.1      .1       0    4985     .05       0  4996.3      .1       0
  5024.4     .07       0
Bank Sta=4985,4996.3
XS Rating Curve= 0 ,0
Exp/Cntr=0.3,0.1

Type RM Length L Ch R = 1 ,26691   ,379,379,379
BEGIN DESCRIPTION:
Fessenden Branch 57.0
END DESCRIPTION:
XS GIS Cut Line= 3
      1860125.02       13982325.        1859825.       13982275.
      1859161.25      13982186.4
#Sta/Elev= 30
  4691.3 2040.44    4742 2038.11  4789.8 2033.53  4819.5  2031.3  4863.7 2028.23
  4906.8 2026.93  4924.5 2025.55  4954.9 2024.79  4962.5 2025.45  4967.6 2024.03
  4975.2 2023.22  4985.3 2023.63  5009.8 2020.58  5010.3 2020.08    5021 2020.08
  5021.5 2020.58  5037.1  2023.2  5045.9 2023.69  5076.2 2023.46  5096.3 2024.48
  5183.3 2033.51  5231.3  2035.2  5334.5 2038.24  5379.9  2038.9  5456.4 2041.56
  5558.8 2043.93  5563.9 2044.72    5621  2045.8    5637 2045.32  5665.1 2046.34
#Mann= 8 ,-1 , 0
  4691.3      .1       0  4789.8     .07       0  4819.5      .1       0
  5009.8     .05       0  5021.5      .1       0  5231.3     .07       0
  5379.9      .1       0  5456.4     .07       0
Bank Sta=5009.8,5021.5
XS Rating Curve= 0 ,0
Exp/Cntr=0.3,0.1

Type RM Length L Ch R = 1 ,26312   ,327,327,327
BEGIN DESCRIPTION:
Fessenden Branch 56.0
END DESCRIPTION:
XS GIS Cut Line= 3
      1860324.99       13981925.      1859993.51     13982001.31
      1859431.57     13982005.39
#Sta/Elev= 30
  4692.3 2040.34  4753.9 2036.42  4801.9 2031.18  4825.7 2027.33  4897.8 2029.05
  4928.3 2028.03  4935.4 2026.64  4940.6 2027.39  4978.3 2021.69  4983.4 2022.29
  4989.9 2019.33  4994.3    2019  4994.8  2018.5    5006    2019  5010.4 2021.26
  5020.7 2021.26  5026.2  2019.1    5061 2024.18    5081 2023.67    5101 2020.84
    5141 2021.44    5151 2022.75    5161 2022.39    5201 2024.84    5221 2024.68
    5281 2027.29    5311 2029.67  5451.2 2034.68  5501.5 2036.04  5594.4  2039.5
#Mann= 5 ,-1 , 0
  4692.3      .1       0  4994.3     .05       0    5006      .1       0
  5451.2     .07       0  5501.5    .035       0
Bank Sta=4994.3,5006
XS Rating Curve= 0 ,0
Exp/Cntr=0.3,0.1

Type RM Length L Ch R = 1 ,25985   ,357,357,357
BEGIN DESCRIPTION:
Fessenden Branch 55.1
END DESCRIPTION:
XS GIS Cut Line= 2
      1860660.45     13981502.09      1859408.42     13981968.55
#Sta/Elev= 30
  4297.9 2043.51  4430.8 2040.61  4491.4 2036.17  4496.8 2034.96  4506.5 2034.43
  4516.4 2035.27  4521.8 2032.34  4546.8 2032.01  4552.1 2030.92  4637.8 2031.18
  4773.3 2029.84  4864.4  2027.8    4880  2025.9  4901.3 2020.35  4919.7 2019.13
  4933.3 2019.47    4944 2018.07  4980.4 2018.22  4991.5 2017.04    4992 2016.54
  5003.3 2017.04  5005.3 2018.35  5010.7 2017.99  5029.4 2022.91  5136.1 2023.97
    5207 2026.71  5317.5 2029.07  5378.3 2032.25  5573.6 2037.84    5634 2040.49
#Mann= 3 ,-1 , 0
  4297.9     .07       0  4991.5     .05       0  5003.3     .07       0
#XS Ineff= 2 , 0
         4847.03 2034.46 5082.69         2033.73
Permanent Ineff=
       F       F
Bank Sta=4991.5,5003.3
XS Rating Curve= 0 ,0
Exp/Cntr=0.3,0.1

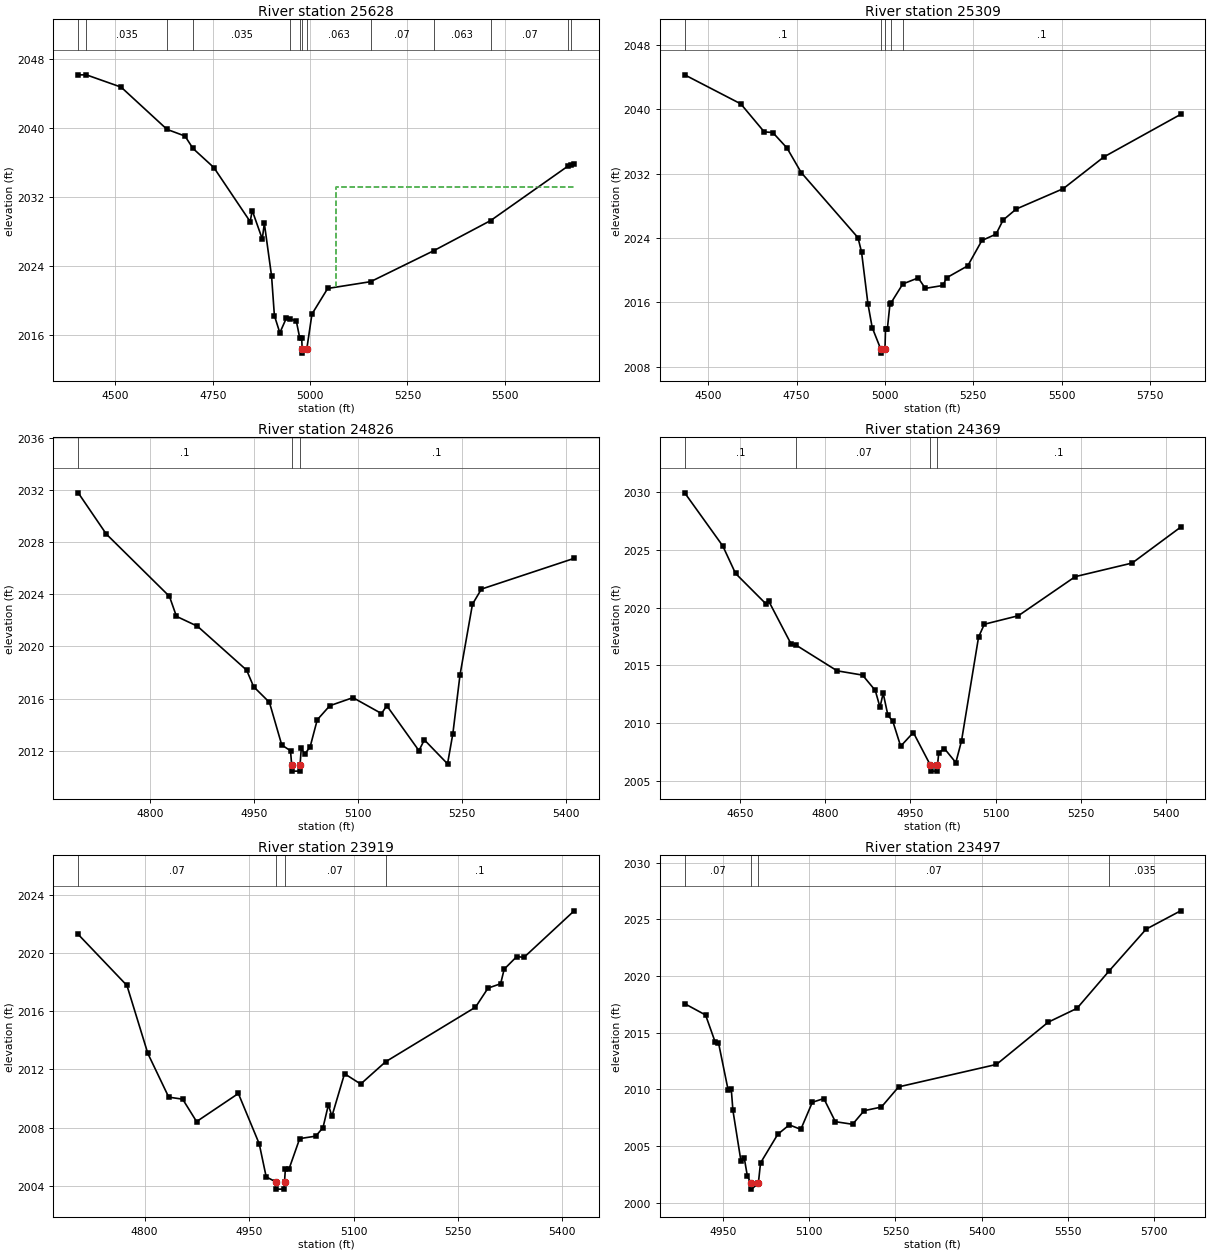
Type RM Length L Ch R = 1 ,25628   ,319,319,319
BEGIN DESCRIPTION:
Fessenden Branch 55.0
END DESCRIPTION:
XS GIS Cut Line= 3
      1860594.13     13981233.84      1860051.95     13981422.39
      1859374.88      13981599.6
#Sta/Elev= 30
  4404.4  2046.2  4425.2 2046.21  4514.6 2044.78  4632.4 2039.87  4678.7 2039.09
  4699.2 2037.65  4752.8 2035.43  4846.1 2029.14  4851.4 2030.43  4877.2 2027.12
  4882.5 2028.94  4901.1  2022.8  4908.3 2018.22  4922.3 2016.21  4939.4 2017.96
  4949.2 2017.82  4964.6 2017.59  4973.2 2015.66  4978.4 2015.62  4979.7 2014.35
  4980.2 2013.85  4991.6 2014.35  5004.8 2018.39  5045.2 2021.37  5155.6 2022.16
  5317.2 2025.75    5464 2029.27  5663.1 2035.62  5669.7 2035.78  5678.3 2035.88
#Mann= 13 ,-1 , 0
  4404.4     .07       0  4425.2    .035       0  4632.4     .07       0
  4699.2    .035       0  4949.2     .07       0  4973.2    .063       0
  4979.7     .05       0  4991.6    .063       0  5155.6     .07       0
  5317.2    .063       0    5464     .07       0  5663.1    .094       0
  5669.7    .063       0
#XS Ineff= 2 , 0
                         5067.44          2033.2
Permanent Ineff=
       F       F
Bank Sta=4979.7,4991.6
XS Rating Curve= 0 ,0
Exp/Cntr=0.3,0.1

Type RM Length L Ch R = 1 ,25309   ,483,483,483
BEGIN DESCRIPTION:
Fessenden Branch 54.0
END DESCRIPTION:
XS GIS Cut Line= 3
      1860543.01     13981067.08        1859975.       13981125.
      1859143.04      13981158.8
#Sta/Elev= 30
  4433.5 2044.29  4592.3 2040.68  4658.6  2037.2  4682.8 2037.12    4723  2035.2
  4763.2 2032.15    4924 2024.05  4934.1 2022.26  4952.2 2015.81  4964.2 2012.88
  4988.4  2010.2  4988.9  2009.7  5000.4  2010.2  5001.9 2012.66    5007 2012.66
  5014.5 2015.82  5016.4 2015.87  5050.9  2018.3  5094.5 2019.05  5114.5 2017.75
  5164.6 2018.11  5174.6 2019.06  5234.6 2020.55  5274.7  2023.7  5314.7 2024.49
  5334.7 2026.24  5371.9 2027.61  5504.9 2030.14  5620.1 2034.09  5837.1 2039.37
#Mann= 5 ,-1 , 0
  4433.5      .1       0  4988.4     .05       0  5000.4      .1       0
  5016.4     .07       0  5050.9      .1       0
Bank Sta=4988.4,5000.4
XS Rating Curve= 0 ,0
Exp/Cntr=0.3,0.1

Type RM Length L Ch R = 1 ,24826   ,457,457,457
BEGIN DESCRIPTION:
Fessenden Branch 53.0
END DESCRIPTION:
XS GIS Cut Line= 3
      1860274.98       13980725.        1859975.       13980675.
      1859575.03     13980575.01
#Sta/Elev= 30
  4695.9 2031.79  4736.4 2028.63  4827.7 2023.84  4837.8 2022.31  4868.2 2021.55
  4939.2 2018.18  4949.3 2016.91  4972.1 2015.71  4989.9 2012.44  5002.6 2011.99
  5004.2 2010.93  5004.7 2010.43  5015.9 2010.43  5016.4 2010.93  5018.1 2012.18
  5023.2 2011.74  5030.9 2012.29  5041.2 2014.37  5059.3 2015.45  5092.8 2016.07
    5134 2014.85  5141.7 2015.45  5188.1    2012  5195.9 2012.83  5229.4 2010.99
  5237.1 2013.31  5247.4 2017.81  5265.4 2023.24  5278.3  2024.4  5412.3 2026.76
#Mann= 3 ,-1 , 0
  4695.9      .1       0  5004.2     .05       0  5016.4      .1       0
Bank Sta=5004.2,5016.4
XS Rating Curve= 0 ,0
Exp/Cntr=0.3,0.1

Type RM Length L Ch R = 1 ,24369   ,450,450,450
BEGIN DESCRIPTION:
Fessenden Branch 52.0
END DESCRIPTION:
XS GIS Cut Line= 3
      1860325.04     13980475.02        1859925.       13980275.
      1859499.77     13980254.22
#Sta/Elev= 30
  4552.7 2029.96  4619.8 2025.35  4642.2 2022.97  4695.3 2020.35  4700.9 2020.54
    4740 2016.85  4749.4 2016.73  4821.1 2014.52  4865.8 2014.15  4888.2 2012.82
  4896.5 2011.36  4902.1 2012.58  4910.5 2010.65  4918.9 2010.17  4932.9 2007.98
  4955.2 2009.17  4985.4 2006.32  4985.9 2005.82  4997.2 2005.82  4997.7 2006.32
    5000 2007.43    5010 2007.77    5030 2006.56    5040 2008.44    5070 2017.44
  5080.1 2018.56  5140.1  2019.3  5240.2 2022.69  5340.4 2023.87  5425.7 2026.98
#Mann= 4 ,-1 , 0
  4552.7      .1       0  4749.4     .07       0  4985.4     .05       0
  4997.7      .1       0
Bank Sta=4985.4,4997.7
XS Rating Curve= 0 ,0
Exp/Cntr=0.3,0.1

Type RM Length L Ch R = 1 ,23919   ,422,422,422
BEGIN DESCRIPTION:
Fessenden Branch 51.0
END DESCRIPTION:
XS GIS Cut Line= 3
      1860375.01       13979875.        1860075.       13979875.
      1859675.02     13979974.99
#Sta/Elev= 30
  4704.6 2021.28  4774.6 2017.77  4804.6  2013.1  4834.6  2010.1  4854.6 2009.96
  4874.6 2008.42  4934.6 2010.35  4964.6 2006.89  4974.6 2004.62  4988.4 2004.28
  4988.9 2003.78  5000.4 2003.78  5000.9 2004.28  5002.1 2005.14  5007.2 2005.14
  5022.7 2007.25  5045.8 2007.42  5056.2 2008.01  5063.9 2009.57    5069 2008.79
  5087.1 2011.71  5110.3    2011  5146.1 2012.53  5275.2 2016.28  5293.2 2017.59
  5311.3 2017.89  5316.4 2018.89  5334.5 2019.76  5344.8  2019.7  5416.9  2022.9
#Mann= 4 ,-1 , 0
  4704.6     .07       0  4988.4     .05       0  5000.9     .07       0
  5146.1      .1       0
Bank Sta=4988.4,5000.9
XS Rating Curve= 0 ,0
Exp/Cntr=0.3,0.1

Type RM Length L Ch R = 1 ,23497   ,452,452,452
BEGIN DESCRIPTION:
Fessenden Branch 50.0
END DESCRIPTION:
XS GIS Cut Line= 3
      1860374.96     13979624.98        1860275.       13979575.
      1859524.96       13979575.
#Sta/Elev= 30
  4883.8 2017.56  4920.1 2016.56  4936.9 2014.16  4942.5 2014.13  4959.2 2009.97
  4964.8    2010  4967.6 2008.15  4981.6 2003.67  4987.2 2003.99  4992.8 2002.33
  4999.3  2001.7  4999.8  2001.2  5011.8  2001.7  5015.6 2003.51  5045.6 2006.04
  5065.6 2006.87  5085.6 2006.47  5105.6 2008.86  5125.6 2009.19  5145.6 2007.15
  5175.6 2006.92  5195.6 2008.12  5225.6 2008.44  5255.6 2010.22  5425.6  2012.2
  5515.6 2015.93  5565.6 2017.15  5620.9 2020.42  5685.6 2024.13  5745.6 2025.75
#Mann= 4 ,-1 , 0
  4883.8     .07       0  4999.3     .05       0  5011.8     .07       0
  5620.9    .035       0
Bank Sta=4999.3,5011.8
XS Rating Curve= 0 ,0
Exp/Cntr=0.3,0.1

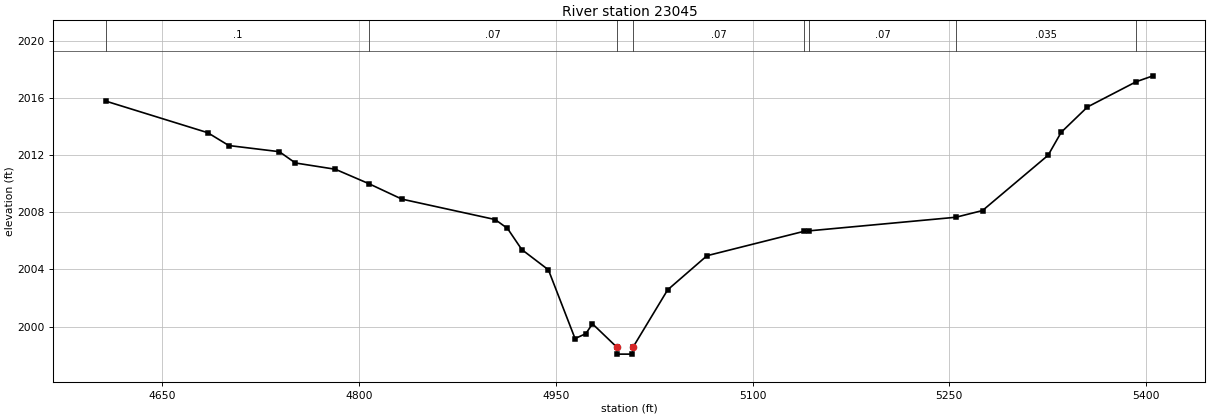
Type RM Length L Ch R = 1 ,23045   ,452,452,452
BEGIN DESCRIPTION:
Fessenden Branch 49.0
END DESCRIPTION:
XS GIS Cut Line= 3
      1860517.37     13979243.16        1860125.       13979175.
      1859724.95       13979175.
#Sta/Elev= 30
    4607 2015.78  4684.7 2013.57  4700.8 2012.67  4739.3 2012.24  4751.5 2011.45
    4782 2011.01  4807.8 2009.99  4832.7 2008.92  4903.8 2007.49  4913.2 2006.87
  4924.1 2005.39  4944.4 2003.97  4964.7 1999.16  4972.9  1999.5    4978 2000.19
  4996.4 1998.57  4996.9 1998.07  5008.5 1998.07    5009 1998.57  5035.3 2002.57
  5065.3 2004.96  5139.4 2006.67  5143.2  2006.7  5254.9 2007.65  5275.3 2008.12
  5325.3 2011.99  5335.3  2013.6  5355.3 2015.37  5392.5 2017.14  5405.3 2017.55
#Mann= 8 ,-1 , 0
    4607      .1       0  4807.8     .07       0  4996.4     .05       0
    5009     .07       0  5139.4      .1       0  5143.2     .07       0
  5254.9    .035       0  5392.5     .07       0
Bank Sta=4996.4,5009
XS Rating Curve= 0 ,0
Exp/Cntr=0.3,0.1