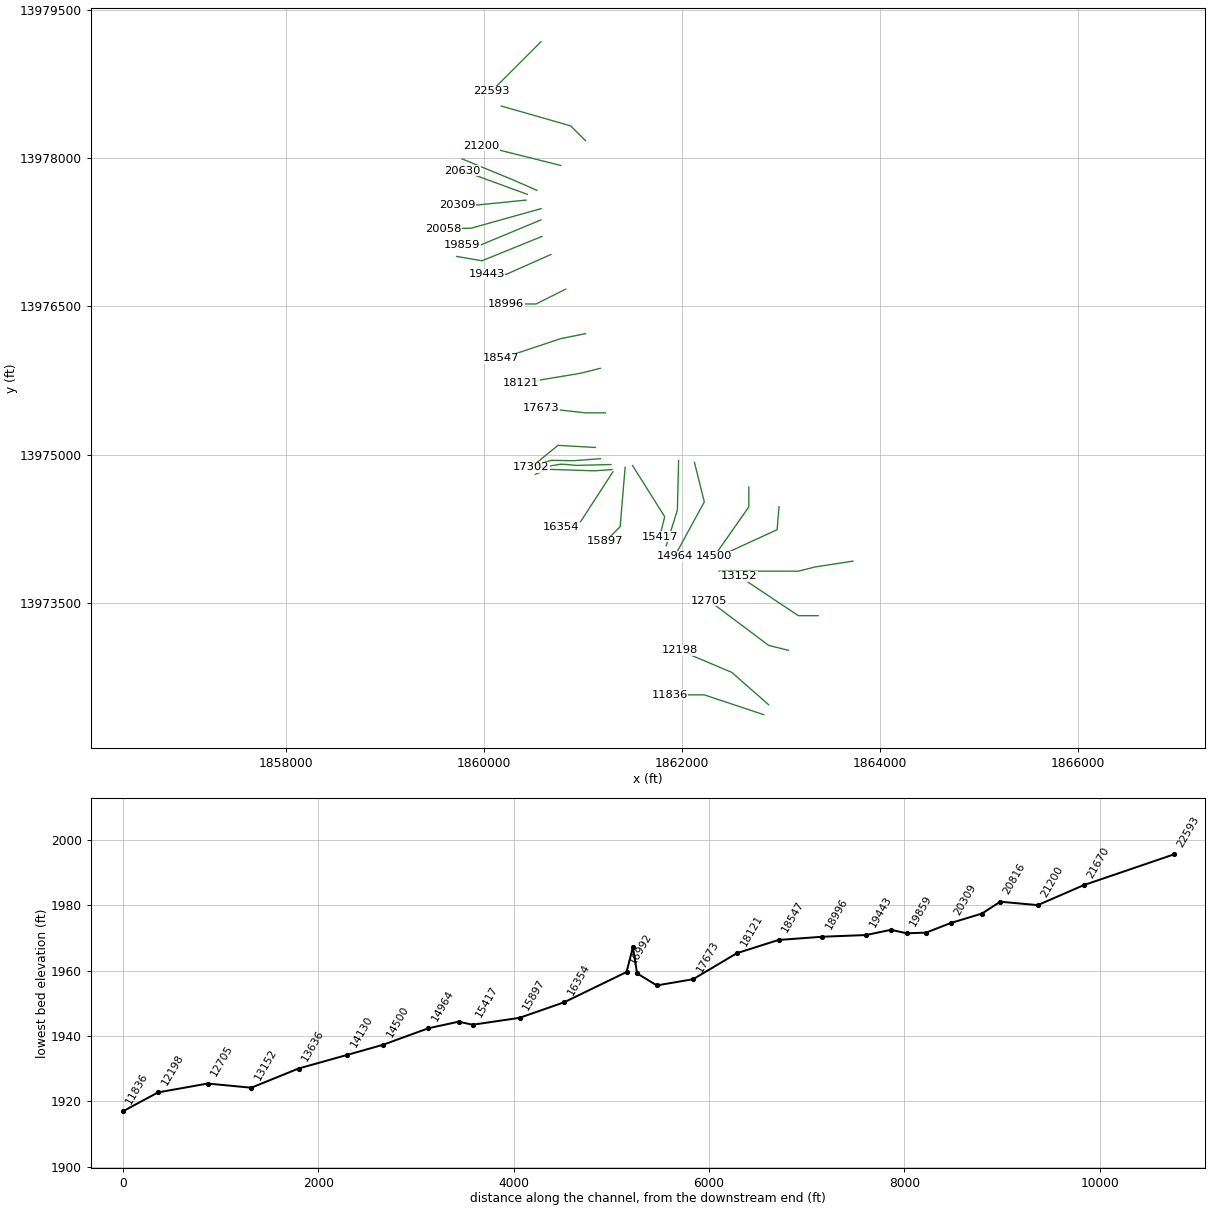
HEC-RAS study Fessenden Branch.prj: Fessenden Branch Base Level Engineering

--- Fessenden Branch.g01 (geometry) --- (continued)

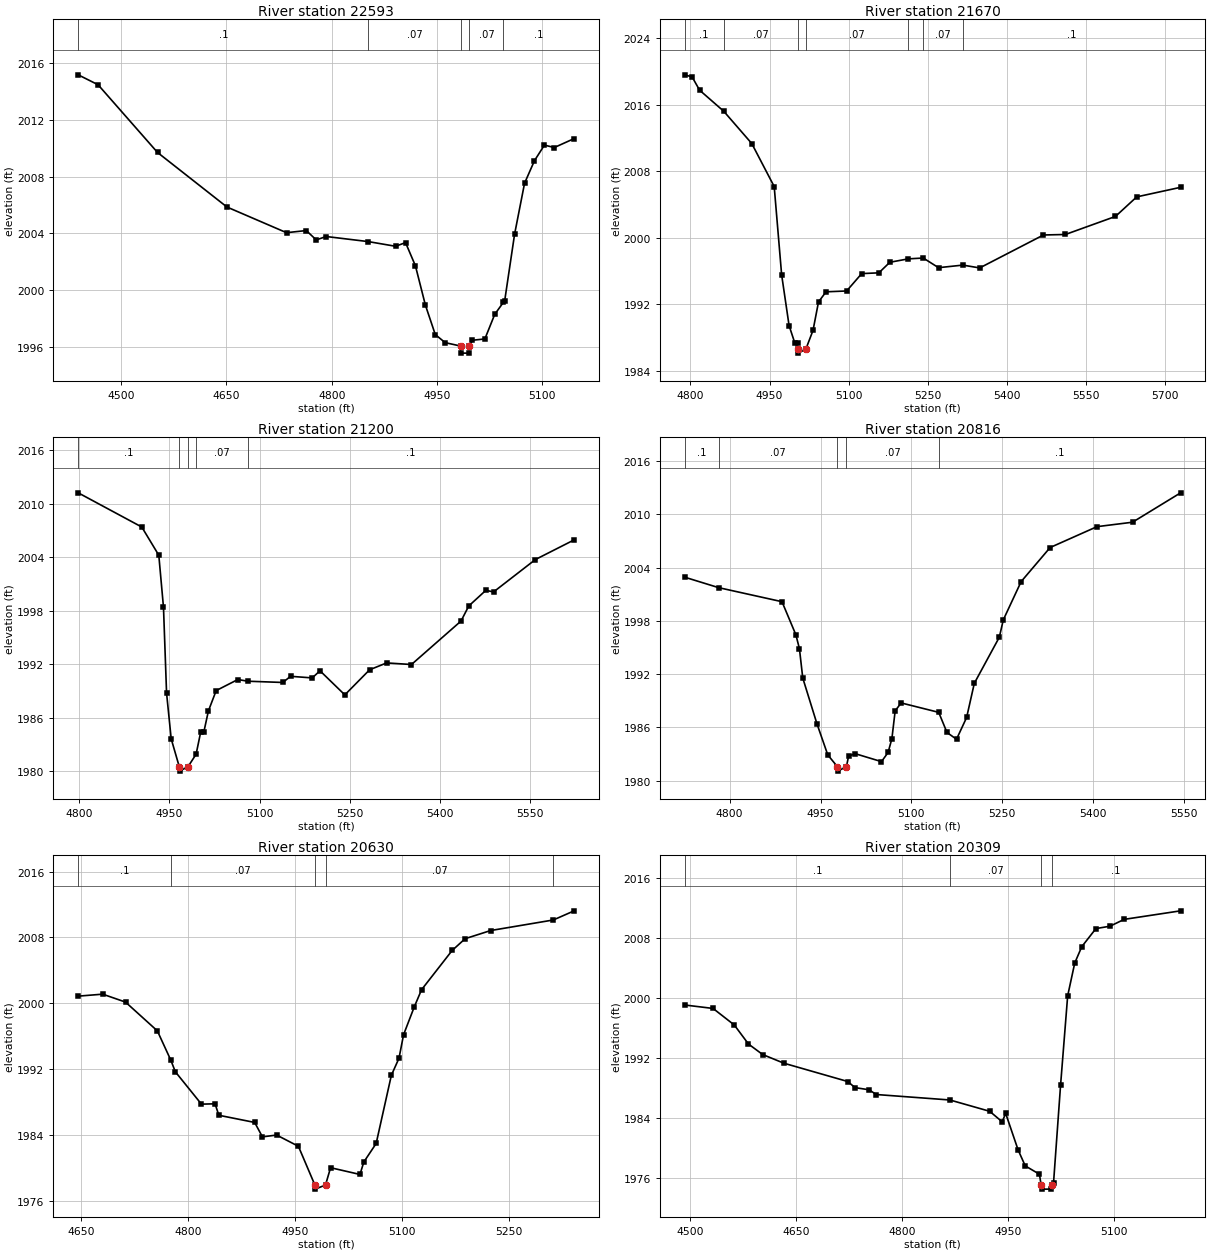
Type RM Length L Ch R = 1 ,22593   ,923,923,923
BEGIN DESCRIPTION:
Fessenden Branch 48.0
END DESCRIPTION:
XS GIS Cut Line= 3
      1860574.98     13979174.98        1860175.       13978775.
      1860074.99     13978674.99
#Sta/Elev= 30
  4438.6 2015.19  4466.9 2014.49  4551.7 2009.71  4650.7 2005.86  4735.6 2004.05
  4763.8  2004.2    4778 2003.54  4792.1 2003.78  4852.3 2003.42  4891.1 2003.09
  4905.3 2003.35  4919.4 2001.71  4933.6 1998.94  4947.7 1996.86  4961.8 1996.29
  4983.8 1996.05  4984.3 1995.55  4995.9 1995.55  4996.4 1996.05  5000.7 1996.46
  5018.4 1996.55  5032.5 1998.29  5044.9 1999.14  5046.7 1999.26  5060.8 2003.95
    5075 2007.54  5089.1 2009.13  5103.3 2010.23  5117.4 2010.06  5145.7 2010.69
#Mann= 5 ,-1 , 0
  4438.6      .1       0  4852.3     .07       0  4983.8     .05       0
  4996.4     .07       0  5044.9      .1       0
Bank Sta=4983.8,4996.4
XS Rating Curve= 0 ,0
Exp/Cntr=0.3,0.1

Type RM Length L Ch R = 1 ,21670   ,470,470,470
BEGIN DESCRIPTION:
Fessenden Branch 47.0
END DESCRIPTION:
XS GIS Cut Line= 3
      1861024.97     13978175.03        1860875.       13978325.
        1860175.       13978525.
#Sta/Elev= 30
  4789.1 2019.59  4803.2 2019.34  4817.3 2017.75  4863.2 2015.21  4916.3 2011.33
  4958.8 2006.16  4972.9 1995.55    4987 1989.45  4997.7 1987.39  5003.8 1987.39
  5004.3 1986.64  5004.8 1986.14  5018.9 1986.64  5032.4 1988.88  5042.8  1992.3
  5057.1 1993.51  5096.1 1993.61  5124.7  1995.7  5157.2 1995.79    5178 1997.06
  5212.9 1997.47  5241.4 1997.57  5270.3 1996.41  5316.4 1996.72  5348.3 1996.38
  5469.2 2000.34  5510.8  2000.4  5605.7 2002.57    5646 2004.92  5729.2 2006.07
#Mann= 7 ,-1 , 0
  4789.1      .1       0  4863.2     .07       0  5004.3     .05       0
  5018.9     .07       0  5212.9      .1       0  5241.4     .07       0
  5316.4      .1       0
Bank Sta=5004.3,5018.9
XS Rating Curve= 0 ,0
Exp/Cntr=0.3,0.1

Type RM Length L Ch R = 1 ,21200   ,384,384,384
BEGIN DESCRIPTION:
Fessenden Branch 46.0
END DESCRIPTION:
XS GIS Cut Line= 3
      1860775.02     13977924.99        1860575.       13977975.
      1859975.04     13978124.99
#Sta/Elev= 30
  4798.5 2011.21  4904.2 2007.38  4932.5 2004.22  4940.3 1998.37  4945.4 1988.78
  4953.1 1983.66  4966.5 1980.54    4967 1980.04  4981.1 1980.54  4994.5 1981.93
  5002.1  1984.4  5007.3  1984.4    5015 1986.79  5027.9 1989.06  5063.9  1990.3
  5080.6 1990.11  5138.7 1989.97  5151.6 1990.66  5187.6 1990.48  5200.5 1991.28
  5241.8 1988.58    5283 1991.39  5311.3 1992.16  5352.6 1991.98    5435 1996.85
  5447.9 1998.54  5476.3 2000.29  5489.1 2000.11  5558.7 2003.74  5623.1 2005.94
#Mann= 5 ,-1 , 0
  4798.5      .1       0  4966.5     .05       0  4981.1      .1       0
  4994.5     .07       0  5080.6      .1       0
Bank Sta=4966.5,4981.1
XS Rating Curve= 0 ,0
Exp/Cntr=0.3,0.1

Type RM Length L Ch R = 1 ,20816   ,186,186,186
BEGIN DESCRIPTION:
Fessenden Branch 45.0
END DESCRIPTION:
XS GIS Cut Line= 3
      1860533.25     13977673.91      1860280.39     13977784.47
      1859778.09      13977990.8
#Sta/Elev= 30
  4725.7 2002.92  4781.9 2001.74  4886.4 2000.16  4909.3 1996.44  4915.2 1994.87
  4920.7 1991.57  4944.1 1986.42    4962 1982.91  4977.9 1981.58  4978.4 1981.08
  4992.8 1981.58  4996.4 1982.78  5007.5 1983.04  5050.7 1982.15  5061.6 1983.18
  5067.9 1984.74  5073.3 1987.87  5083.2 1988.76  5145.2  1987.7  5158.9 1985.43
  5174.6 1984.67  5191.3 1987.12    5204 1990.97  5245.3 1996.16  5251.9 1998.12
  5281.3 2002.42  5329.2 2006.26  5406.6 2008.61  5465.3 2009.11  5544.7 2012.42
#Mann= 5 ,-1 , 0
  4725.7      .1       0  4781.9     .07       0  4977.9     .05       0
  4992.8     .07       0  5145.2      .1       0
Bank Sta=4977.9,4992.8
XS Rating Curve= 0 ,0
Exp/Cntr=0.3,0.1

Type RM Length L Ch R = 1 ,20630   ,321,321,321
BEGIN DESCRIPTION:
Mapping XS 2cc883fb
END DESCRIPTION:
XS GIS Cut Line= 2
      1860437.25     13977633.09      1859784.39     13977871.69
#Sta/Elev= 30
  4645.9 2000.88  4680.2 2001.12  4712.2 2000.16  4756.8 1996.67  4775.8 1993.09
    4782 1991.71  4818.6 1987.78  4837.7 1987.82    4843 1986.43  4893.2 1985.56
  4904.1 1983.81    4924 1984.03  4954.5 1982.67  4977.6 1977.97  4978.1 1977.47
  4992.5 1977.97  4999.6 1980.07  5040.8 1979.25  5046.2 1980.76  5063.5 1983.01
  5084.8 1991.28  5095.5 1993.35  5101.9  1996.2  5116.8 1999.55  5127.1 2001.66
    5170 2006.42  5188.2 2007.85    5224 2008.84  5311.8 2010.12    5341 2011.23
#Mann= 5 ,-1 , 0
  4645.9      .1       0  4775.8     .07       0  4977.6     .05       0
  4992.5     .07       0  5311.8      .1       0
Bank Sta=4977.6,4992.5
XS Rating Curve= 0 ,0
Exp/Cntr=0.3,0.1

Type RM Length L Ch R = 1 ,20309   ,251,251,251
BEGIN DESCRIPTION:
Fessenden Branch 44.0
END DESCRIPTION:
XS GIS Cut Line= 3
      1860424.96       13977575.        1859925.       13977525.
      1859724.95       13977525.
#Sta/Elev= 30
  4492.5 1999.12  4532.7 1998.66  4562.8 1996.45  4582.9 1993.91    4603 1992.51
  4633.2 1991.35  4723.6 1988.91  4733.7  1988.1  4753.8 1987.81  4763.8 1987.18
  4868.2 1986.45  4924.6 1984.94  4942.2 1983.54  4947.2 1984.66  4964.8 1979.79
  4974.9 1977.66    4995 1976.55  4997.5 1975.06    4998 1974.56    5012 1974.56
  5012.5 1975.06    5015 1975.41    5025 1988.49    5035 2000.34    5045 2004.71
    5055  2006.9    5075 2009.31    5095 2009.63    5115 2010.54    5195 2011.68
#Mann= 4 ,-1 , 0
  4492.5      .1       0  4868.2     .07       0  4997.5     .05       0
  5012.5      .1       0
Bank Sta=4997.5,5012.5
XS Rating Curve= 0 ,0
Exp/Cntr=0.3,0.1

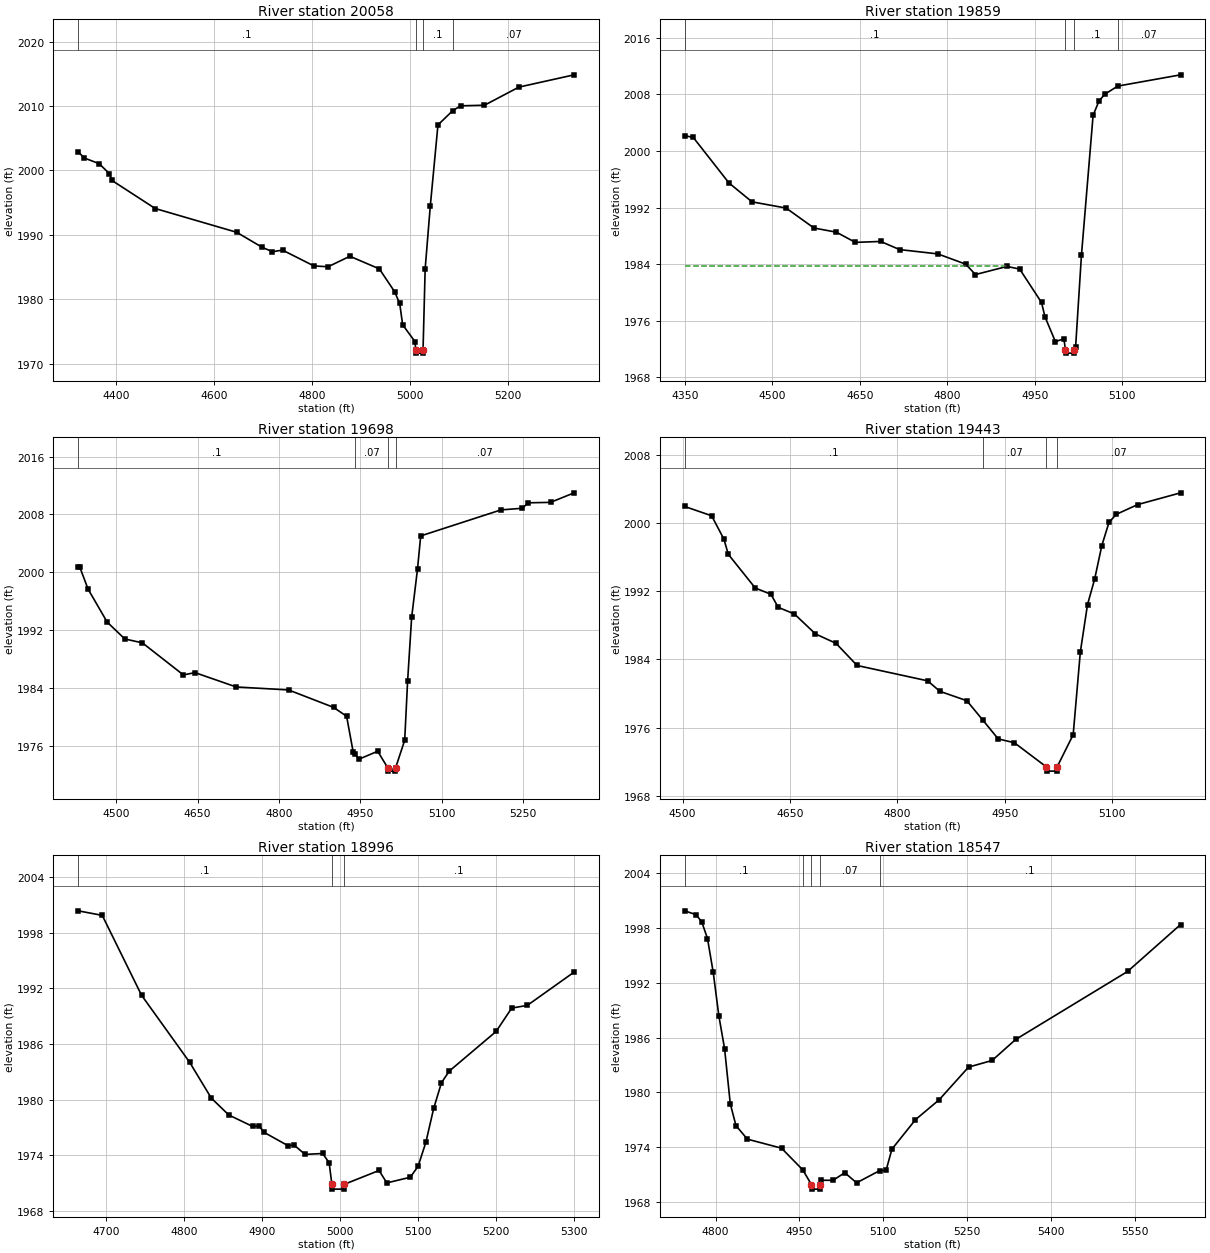
Type RM Length L Ch R = 1 ,20058   ,199,199,199
BEGIN DESCRIPTION:
Mapping XS ff5965a5
END DESCRIPTION:
XS GIS Cut Line= 3
      1860576.24     13977488.56      1859869.74     13977290.74
      1859592.25     13977285.86
#Sta/Elev= 30
  4323.5 2002.91  4335.2 2001.95  4366.3 2001.04  4387.1 1999.49  4392.3 1998.44
  4480.6 1994.08  4646.7 1990.39  4698.6 1988.06  4719.4 1987.38  4740.2 1987.62
    4804 1985.17  4832.9 1985.04  4877.4 1986.67  4937.5 1984.71  4968.6 1981.17
    4979 1979.34    4985 1976.03  5010.2 1973.42  5011.6 1972.13  5012.1 1971.63
  5026.1 1971.63  5026.6 1972.13  5030.9 1984.71  5041.3 1994.41    5057 2007.06
  5086.9 2009.26  5103.2 2010.03  5151.9 2010.12  5221.9 2012.93  5334.7 2014.84
#Mann= 4 ,-1 , 0
  4323.5      .1       0  5011.6     .05       0  5026.6      .1       0
  5086.9     .07       0
#XS Ineff= 2 , 0
         4877.52 1986.34
Permanent Ineff=
       F       F
Bank Sta=5011.6,5026.6
XS Rating Curve= 0 ,0
Exp/Cntr=0.3,0.1

Type RM Length L Ch R = 1 ,19859   ,161,161,161
BEGIN DESCRIPTION:
Fessenden Branch 43.0
END DESCRIPTION:
XS GIS Cut Line= 3
      1860575.02     13977375.01        1859975.       13977125.
      1859775.03       13977125.
#Sta/Elev= 30
  4349.9 2002.17  4364.6 2001.92  4425.8 1995.48  4465.3 1992.81  4523.8 1991.93
  4571.5 1989.11  4609.9 1988.52  4642.4 1987.08  4685.8 1987.21  4718.3 1986.06
  4783.8 1985.45  4831.5    1984  4848.3 1982.53  4902.4 1983.68  4924.1  1983.3
  4961.5 1978.58  4967.4 1976.56  4985.3 1973.04  4999.9 1973.45  5002.4 1971.92
  5002.9 1971.42  5016.9 1971.42  5017.4 1971.92  5019.9 1972.26  5029.9 1985.24
  5049.9 2005.05  5059.9 2007.05  5069.9 2008.03  5092.3 2009.18  5199.9 2010.77
#Mann= 4 ,-1 , 0
  4349.9      .1       0  5002.4     .05       0  5017.4      .1       0
  5092.3     .07       0
#XS Ineff= 2 , 0
         4901.55 1983.81
Permanent Ineff=
       F       F
Bank Sta=5002.4,5017.4
XS Rating Curve= 0 ,0
Exp/Cntr=0.3,0.1

Type RM Length L Ch R = 1 ,19698   ,255,255,255
BEGIN DESCRIPTION:
Mapping XS 7e19f8cc
END DESCRIPTION:
XS GIS Cut Line= 3
      1860584.61     13977207.66      1859978.93     13976961.81
      1859722.01      13977005.6
#Sta/Elev= 30
  4429.9 2000.79  4432.4 2000.79    4448 1997.67  4483.4 1993.09  4515.8 1990.77
  4548.2 1990.23  4623.7  1985.8  4645.3 1986.11  4721.2 1984.13  4817.6 1983.72
  4900.6 1981.31  4924.7 1980.08  4936.7 1975.19  4940.7  1974.8  4947.5 1974.14
    4982 1975.24  5000.2 1972.99  5000.7 1972.49  5014.7 1972.49  5015.2 1972.99
  5031.8 1976.76  5037.2 1984.99  5044.6 1993.75  5055.4 2000.43  5061.3 2005.02
  5209.3 2008.62  5248.1 2008.84    5260  2009.6  5300.6 2009.66  5344.2 2010.98
#Mann= 4 ,-1 , 0
  4429.9      .1       0  4940.7     .07       0  5000.2     .05       0
  5015.2     .07       0
Bank Sta=5000.2,5015.2
XS Rating Curve= 0 ,0
Exp/Cntr=0.3,0.1

Type RM Length L Ch R = 1 ,19443   ,447,447,447
BEGIN DESCRIPTION:
Fessenden Branch 42.0
END DESCRIPTION:
XS GIS Cut Line= 3
        1860675.       13977025.        1860225.       13976825.
      1860025.04       13976825.
#Sta/Elev= 30
    4503 2001.93  4540.6 2000.84  4557.7 1998.11  4563.9 1996.32  4601.5 1992.37
  4623.4 1991.63  4633.6  1990.1  4656.2 1989.32  4685.6 1986.98  4714.3 1985.88
  4743.7 1983.28  4842.2 1981.48  4859.3 1980.25  4896.9 1979.15  4919.4 1976.86
  4940.7 1974.67  4963.3 1974.22  5007.9 1971.39  5008.4 1970.89  5022.5 1970.89
    5023 1971.39  5045.4 1975.16  5055.4 1984.87  5065.4 1990.42  5075.4 1993.42
  5085.4 1997.35  5095.4 2000.06  5105.4    2001  5135.4 2002.15  5195.4 2003.53
#Mann= 4 ,-1 , 0
    4503      .1       0  4919.4     .07       0  5007.9     .05       0
    5023     .07       0
Bank Sta=5007.9,5023
XS Rating Curve= 0 ,0
Exp/Cntr=0.3,0.1

Type RM Length L Ch R = 1 ,18996   ,449,449,449
BEGIN DESCRIPTION:
Fessenden Branch 41.0
END DESCRIPTION:
XS GIS Cut Line= 3
      1860825.03     13976675.02        1860525.       13976525.
      1860225.05       13976525.
#Sta/Elev= 30
  4664.8 2000.36  4695.6 1999.87  4745.9 1991.27  4807.4 1984.06  4835.3 1980.18
  4857.7 1978.36  4888.4 1977.12  4896.8 1977.18  4902.4 1976.51  4933.2 1975.07
  4941.6  1975.1  4955.5 1974.11  4977.9 1974.21  4986.3 1973.22  4989.8 1970.87
  4990.3 1970.37  5004.7 1970.37  5005.2 1970.87  5050.2 1972.38  5060.2 1971.04
  5090.2 1971.65  5100.2 1972.82  5110.2 1975.41  5120.2 1979.06  5130.2 1981.84
  5140.2 1983.09  5200.2 1987.36  5220.2 1989.88  5240.2 1990.17  5300.2 1993.76
#Mann= 3 ,-1 , 0
  4664.8      .1       0  4989.8     .05       0  5005.2      .1       0
Bank Sta=4989.8,5005.2
XS Rating Curve= 0 ,0
Exp/Cntr=0.3,0.1

Type RM Length L Ch R = 1 ,18547   ,426,426,426
BEGIN DESCRIPTION:
Fessenden Branch 40.0
END DESCRIPTION:
XS GIS Cut Line= 3
      1861024.97     13976224.99        1860775.       13976175.
      1860174.98     13975974.99
#Sta/Elev= 30
  4744.8  1999.9  4765.2 1999.48  4775.4 1998.68  4785.6 1996.86  4795.8 1993.18
    4806 1988.36  4816.2 1984.78  4826.4 1978.74  4836.6 1976.34    4857 1974.86
  4918.1 1973.87  4956.1 1971.49  4971.6 1969.88  4972.1 1969.38  4986.5 1969.38
    4987 1969.88  4989.5 1970.35  5010.3 1970.35  5031.3 1971.18  5052.4 1970.07
    5094 1971.42  5105.1 1971.43  5115.7 1973.77  5157.8    1977    5200 1979.17
  5252.7 1982.76  5294.9 1983.49    5337 1985.79  5537.3 1993.25  5632.2  1998.4
#Mann= 5 ,-1 , 0
  4744.8      .1       0  4956.1     .07       0  4971.6     .05       0
    4987     .07       0    5094      .1       0
Bank Sta=4971.6,4987
XS Rating Curve= 0 ,0
Exp/Cntr=0.3,0.1

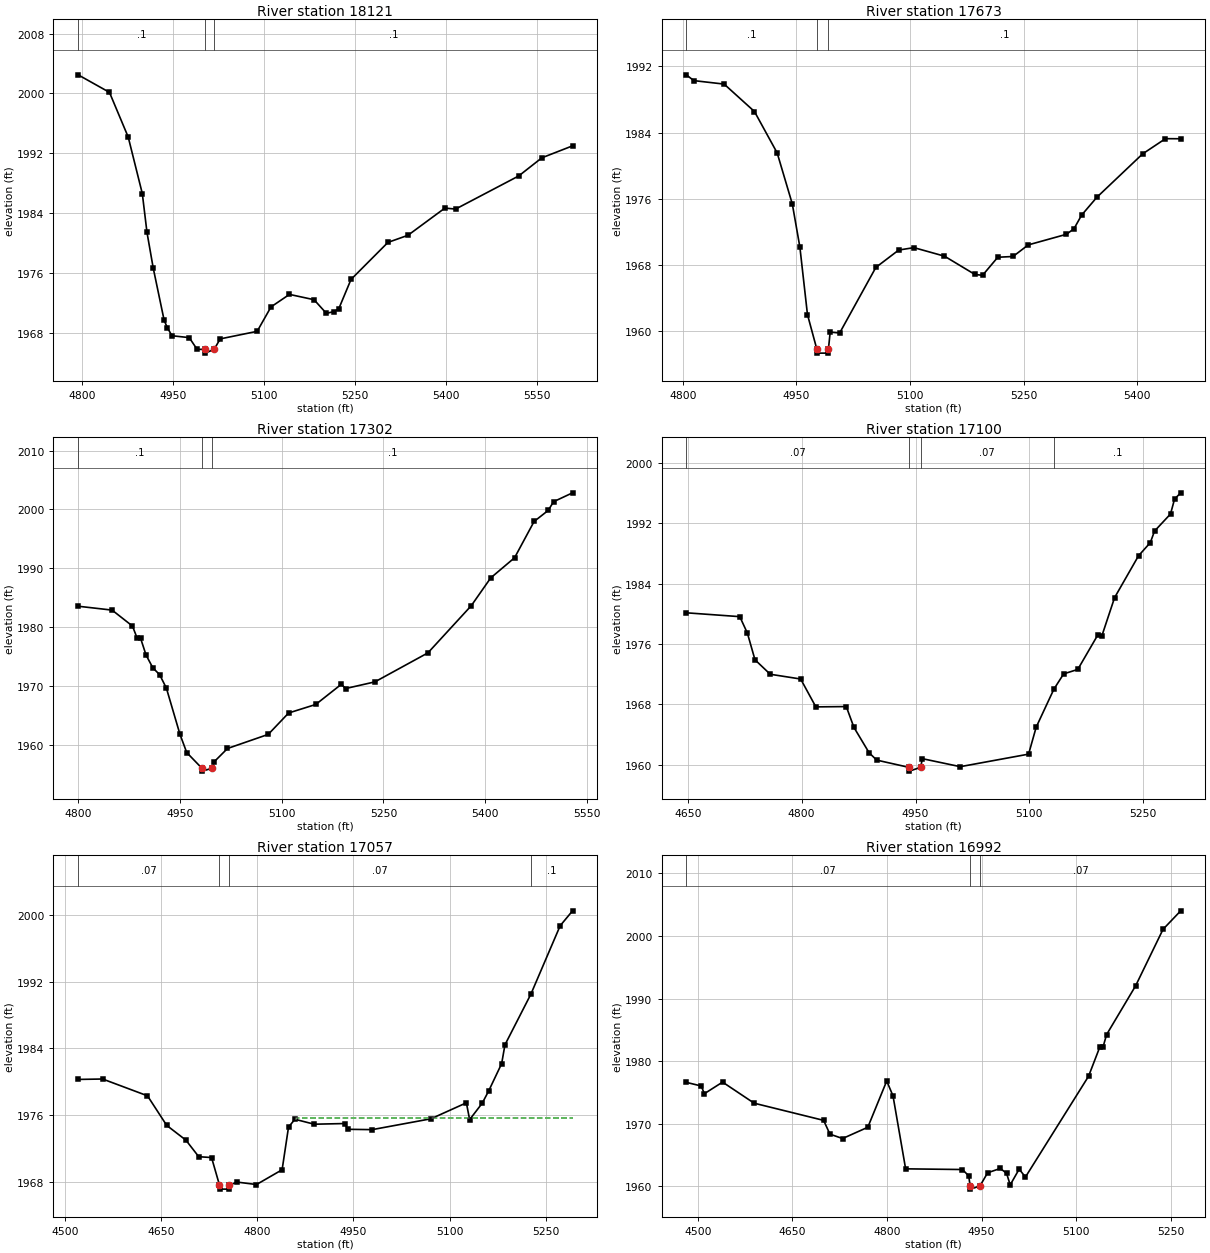
Type RM Length L Ch R = 1 ,18121   ,448,448,448
BEGIN DESCRIPTION:
Fessenden Branch 39.0
END DESCRIPTION:
XS GIS Cut Line= 3
      1861175.01       13975875.        1860975.       13975825.
      1860375.04     13975725.01
#Sta/Elev= 30
  4793.5 2002.49  4845.1 2000.15    4876 1994.18  4899.2 1986.64  4906.9 1981.46
  4917.2 1976.69  4935.2 1969.71  4940.4 1968.74  4948.1 1967.66  4976.5 1967.41
  4989.4 1965.85  5002.1 1965.84  5002.6 1965.34  5017.5 1965.84  5027.5 1967.24
  5088.4 1968.25  5111.2 1971.51  5141.6 1973.18  5182.1 1972.47  5202.4 1970.65
  5215.1 1970.89  5222.7 1971.24    5243 1975.18  5303.8 1980.12  5336.8 1981.07
  5397.6  1984.7  5415.3 1984.57  5519.2 1988.99  5557.3 1991.41  5607.9 1993.01
#Mann= 3 ,-1 , 0
  4793.5      .1       0  5002.1     .05       0  5017.5      .1       0
Bank Sta=5002.1,5017.5
XS Rating Curve= 0 ,0
Exp/Cntr=0.3,0.1

Type RM Length L Ch R = 1 ,17673   ,371,371,371
BEGIN DESCRIPTION:
Fessenden Branch 38.0
END DESCRIPTION:
XS GIS Cut Line= 3
      1861225.01       13975425.        1861025.       13975425.
      1860574.98       13975475.
#Sta/Elev= 30
  4804.6 1990.99  4814.6 1990.29  4854.6 1989.87  4894.6 1986.56  4924.6 1981.56
  4944.6 1975.39  4954.6 1970.18  4964.6 1962.04  4976.9 1957.88  4977.4 1957.38
  4991.8 1957.38  4992.3 1957.88  4994.6 1959.92  5007.1 1959.81  5054.9 1967.73
  5085.1 1969.83  5105.2 1970.12  5145.5 1969.09  5185.7 1966.88  5195.8 1966.78
  5215.9 1968.96    5236 1969.05  5256.1 1970.45  5306.5 1971.73  5316.5  1972.4
  5326.6 1974.05  5346.7  1976.2  5407.1 1981.44  5437.3 1983.28  5457.4 1983.27
#Mann= 3 ,-1 , 0
  4804.6      .1       0  4976.9     .05       0  4992.3      .1       0
Bank Sta=4976.9,4992.3
XS Rating Curve= 0 ,0
Exp/Cntr=0.3,0.1

Type RM Length L Ch R = 1 ,17302   ,202,202,202
BEGIN DESCRIPTION:
Fessenden Branch 37.0
END DESCRIPTION:
XS GIS Cut Line= 3
        1861125.       13975075.      1860746.61     13975096.22
      1860474.98     13974874.99
#Sta/Elev= 30
  4799.6 1983.53  4849.7 1982.87  4879.7 1980.16  4886.8 1978.06  4891.8 1978.05
  4899.8 1975.22  4909.8 1973.05  4919.8 1971.89  4929.8 1969.59  4949.8 1961.74
  4959.8 1958.64  4982.1 1955.98  4982.6 1955.48  4997.6 1955.98  4999.9 1957.03
  5019.9 1959.33    5080 1961.73  5110.1 1965.37  5150.1 1966.82  5187.8 1970.25
  5194.2 1969.53  5237.3 1970.66  5315.6  1975.6  5379.5 1983.62  5408.2 1988.35
  5443.4 1991.78  5472.2 1997.95    5493 1999.83  5500.9 2001.31  5528.9 2002.82
#Mann= 3 ,-1 , 0
  4799.6      .1       0  4982.1     .05       0  4997.6      .1       0
Bank Sta=4982.1,4997.6
XS Rating Curve= 0 ,0
Exp/Cntr=0.3,0.1

Type RM Length L Ch R = 1 ,17100   ,43,43,43
BEGIN DESCRIPTION:
Fessenden Branch 36.1
END DESCRIPTION:
XS GIS Cut Line= 4
      1861175.26     13974961.48      1860896.18     13974940.99
      1860677.66     13974945.08      1860532.23     13974897.51
#Sta/Elev= 30
    4648 1980.12  4718.5 1979.61  4728.5 1977.43  4738.5  1973.9  4758.6 1971.98
  4798.7 1971.35  4818.7 1967.66  4858.8  1967.7  4868.9 1964.94  4888.9 1961.58
  4898.9 1960.61  4941.3 1959.65  4941.8 1959.15  4956.8 1959.65    4959  1960.8
    5009 1959.74    5099  1961.4    5109 1964.97  5132.3    1970  5145.2 1972.03
  5163.8 1972.62  5190.5 1977.24  5195.7 1977.11  5212.3 1982.13  5243.9 1987.68
  5259.4 1989.42  5264.9 1990.94    5286 1993.21  5291.3 1995.18  5299.4 1996.01
#Mann= 4 ,-1 , 0
    4648     .07       0  4941.3     .05       0  4956.8     .07       0
  5132.3      .1       0
Bank Sta=4941.3,4956.8
XS Rating Curve= 0 ,0
Exp/Cntr=0.3,0.1

Type RM Length L Ch R = 1 ,17057   ,65,65,65
BEGIN DESCRIPTION:
Fessenden Branch 36.2
END DESCRIPTION:
XS GIS Cut Line= 5
      1861283.18     13974902.46      1860929.44     13974893.78
      1860817.67     13974904.63      1860771.01     13974905.72
      1860515.99     13974862.31
#Sta/Elev= 30
  4520.5 1980.28  4558.7 1980.33  4628.7 1978.32  4658.7 1974.78  4688.7 1973.01
  4708.7 1971.03  4728.7 1970.93    4741 1967.65  4741.5 1967.15    4756 1967.15
  4756.5 1967.65  4768.8 1967.99  4798.8  1967.7  4838.8 1969.47  4848.8 1974.58
  4858.8 1975.51  4888.9 1974.92  4936.4    1975  4941.4 1974.31  4979.3 1974.27
  5071.1 1975.57  5126.3 1977.48  5131.4 1975.47    5151 1977.43  5161.1  1978.9
  5181.4 1982.18  5186.5 1984.42    5227 1990.49  5272.7 1998.68    5292 2000.46
#Mann= 4 ,-1 , 0
  4520.5     .07       0    4741     .05       0  4756.5     .07       0
    5227      .1       0
#XS Ineff= 2 , 0
                         4860.54         1975.62
Permanent Ineff=
       F       F
Bank Sta=4741,4756.5
XS Rating Curve= 0 ,0
Exp/Cntr=0.3,0.1

Type RM Length L Ch R = 1 ,16992   ,638,638,638
BEGIN DESCRIPTION:
Fessenden Branch 35.1
END DESCRIPTION:
XS GIS Cut Line= 4
      1861292.43     13974851.86      1861119.09      13974838.9
      1860634.76     13974854.68       1860519.4     13974804.05
#Sta/Elev= 30
  4481.5 1976.63  4505.2 1976.05  4510.2 1974.82  4539.1 1976.67  4589.2  1973.3
  4699.4 1970.56  4709.4 1968.36  4729.5 1967.66  4769.5 1969.46  4799.5 1976.85
  4809.5 1974.46  4829.5 1962.82  4919.6 1962.71  4929.6  1961.7  4931.8 1960.08
  4932.3 1959.58  4947.4 1960.08  4959.6 1962.19  4979.6 1962.88  4989.6 1962.12
  4995.4 1960.25  5009.6 1962.77  5019.6 1961.51  5119.7  1977.6  5137.3  1982.2
  5142.5  1982.2  5148.3 1984.25  5194.3 1992.03  5237.9 2001.07  5265.9 2004.02
#Mann= 3 ,-1 , 0
  4481.5     .07       0  4931.8     .05       0  4947.4     .07       0
#XS Ineff= 2 , 0
         4796.64  1976.1
Permanent Ineff=
       F       F
Bank Sta=4931.8,4947.4
XS Rating Curve= 0 ,0
Exp/Cntr=0.3,0.1

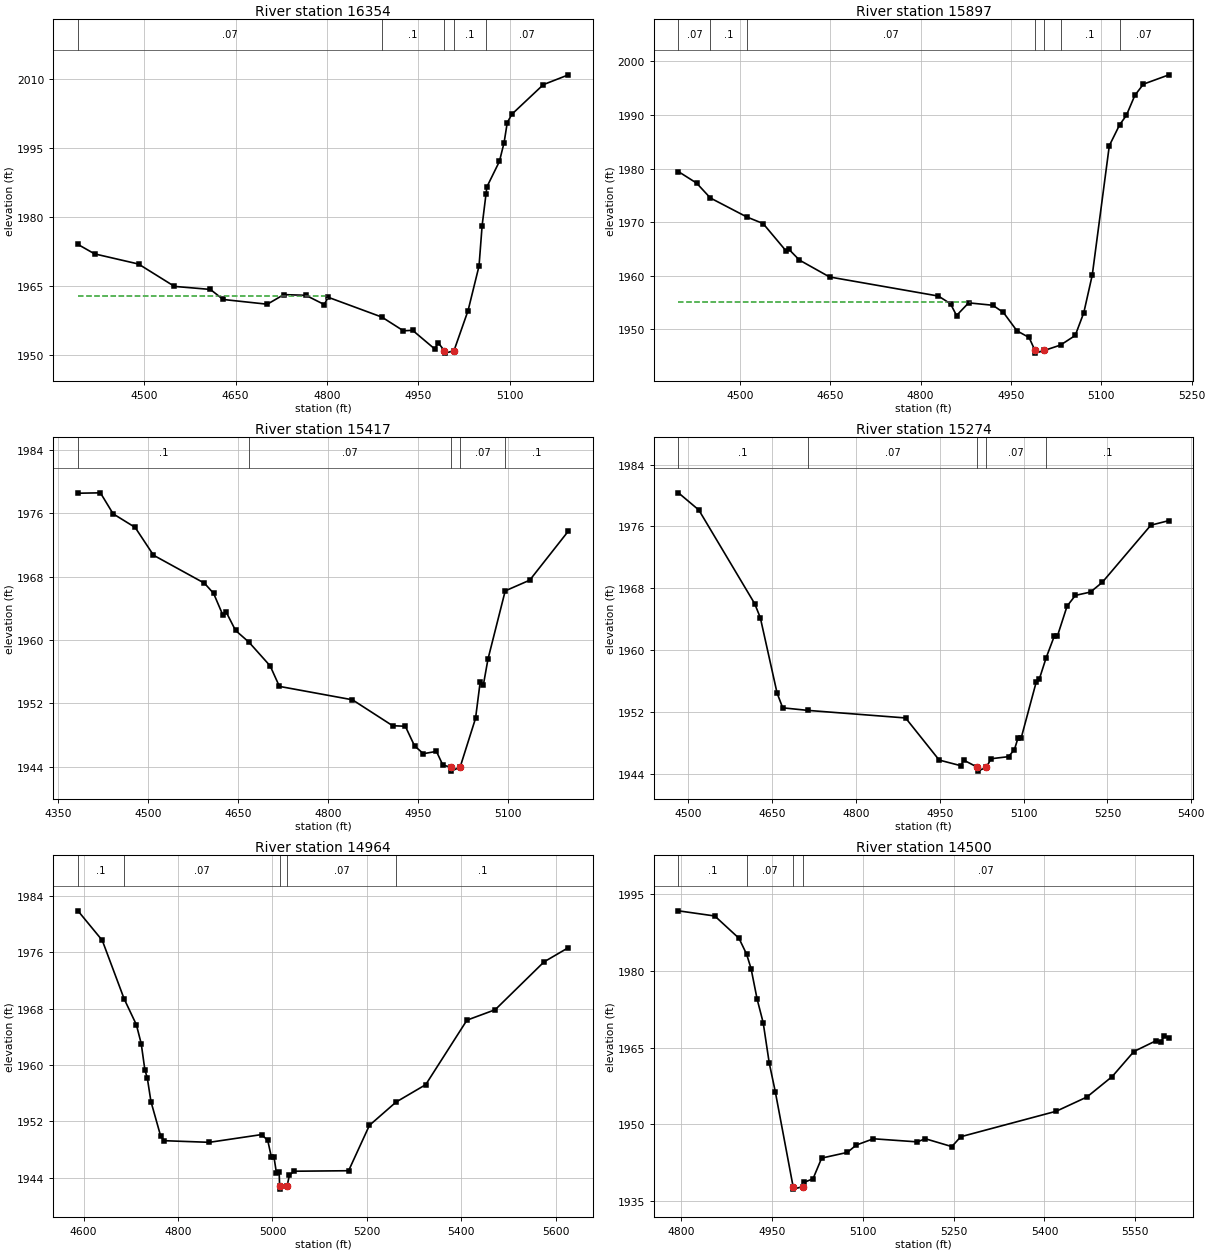
Type RM Length L Ch R = 1 ,16354   ,457,457,457
BEGIN DESCRIPTION:
Fessenden Branch 35.0
END DESCRIPTION:
XS GIS Cut Line= 3
      1861301.17     13974828.03        1860975.       13974325.
      1860774.98     13974274.99
#Sta/Elev= 30
    4391    1974  4418.4 1971.94  4490.5 1969.73  4549.5 1964.86  4608.5  1964.2
  4629.6 1962.01  4702.1 1960.98  4729.1 1963.07  4765.4 1962.92  4795.7  1960.9
  4801.7 1962.51  4890.2 1958.18  4925.6 1955.19  4940.7  1955.3    4977 1951.24
  4982.9 1952.57    4993 1950.83  4993.5 1950.33  5008.6 1950.83  5031.8  1959.6
  5049.8 1969.29  5054.9 1978.11  5061.2  1984.9  5062.7 1986.52  5083.3 1992.08
    5091 1996.19  5096.2 2000.54  5103.9 2002.37  5155.4 2008.79  5196.7 2010.93
#Mann= 5 ,-1 , 0
    4391     .07       0  4890.2      .1       0    4993     .05       0
  5008.6      .1       0  5061.2     .07       0
#XS Ineff= 2 , 0
          4800.4 1962.85
Permanent Ineff=
       F       F
Bank Sta=4993,5008.6
XS Rating Curve= 0 ,0
Exp/Cntr=0.3,0.1

Type RM Length L Ch R = 1 ,15897   ,480,480,480
BEGIN DESCRIPTION:
Fessenden Branch 34.0
END DESCRIPTION:
XS GIS Cut Line= 3
        1861425.     13974874.99        1861375.       13974275.
        1861225.       13974125.
#Sta/Elev= 30
    4398 1979.44  4428.1  1977.3    4451 1974.52  4511.6 1970.97  4538.5 1969.75
  4576.1 1964.71  4581.1 1964.97  4598.7 1962.94  4648.9 1959.78  4829.5 1956.22
  4849.6 1954.78  4859.6 1952.59  4879.7 1954.95  4919.8  1954.5  4937.4 1953.16
  4959.9 1949.73    4980 1948.49  4989.8 1946.07  4990.3 1945.57  5005.4 1946.07
  5032.3 1947.08  5056.6 1948.86  5070.8  1953.1  5084.9 1960.14  5113.2 1984.28
  5130.3 1988.17  5141.5 1989.93  5155.6 1993.67  5169.8 1995.76  5212.2  1997.5
#Mann= 7 ,-1 , 0
    4398     .07       0    4451      .1       0  4511.6     .07       0
  4989.8     .05       0  5005.4     .07       0  5032.3      .1       0
  5130.3     .07       0
#XS Ineff= 2 , 0
         4882.12 1955.09
Permanent Ineff=
       F       F
Bank Sta=4989.8,5005.4
XS Rating Curve= 0 ,0
Exp/Cntr=0.3,0.1

Type RM Length L Ch R = 1 ,15417   ,143,143,143
BEGIN DESCRIPTION:
Fessenden Branch 33.0
END DESCRIPTION:
XS GIS Cut Line= 3
      1861500.26     13974891.97        1861825.       13974375.
      1861774.99     13974174.96
#Sta/Elev= 30
  4383.7 1978.52  4421.1 1978.57  4442.3 1975.92  4478.9 1974.21  4509.5  1970.7
  4594.3 1967.17  4609.6 1965.88  4624.9 1963.16  4630.8 1963.48  4646.1 1961.21
  4668.4 1959.73  4703.8 1956.73  4719.1 1954.15  4840.7 1952.46  4907.6 1949.19
  4928.8 1949.12  4944.1 1946.65  4958.8 1945.66  4980.6 1945.95  4991.2 1944.23
  5004.4 1943.96  5004.9 1943.46    5020 1943.96  5045.7 1950.12  5053.5 1954.75
  5058.6 1954.28  5066.4 1957.59  5095.1  1966.2  5135.9 1967.55  5200.4 1973.76
#Mann= 5 ,-1 , 0
  4383.7      .1       0  4668.4     .07       0  5004.4     .05       0
    5020     .07       0  5095.1      .1       0
Bank Sta=5004.4,5020
XS Rating Curve= 0 ,0
Exp/Cntr=0.3,0.1

Type RM Length L Ch R = 1 ,15274   ,310,310,310
BEGIN DESCRIPTION:
Mapping XS bf798c70
END DESCRIPTION:
XS GIS Cut Line= 3
        1861965.     13974941.53      1861953.22      13974443.3
      1861839.69     13974081.05
#Sta/Elev= 30
  4482.1 1980.35  4518.6 1978.13  4618.7 1966.01  4628.7  1964.2  4658.7 1954.47
  4668.7 1952.57  4713.5 1952.24  4888.7 1951.26  4948.8 1945.82  4987.6 1945.09
  4992.8 1945.81  5017.3 1944.89  5017.8 1944.39  5033.3 1944.89  5041.6 1945.99
    5073 1946.26  5083.5 1947.18  5090.1 1948.71  5095.4 1948.62  5122.6 1955.93
  5127.8 1956.23  5140.4 1959.06    5155 1961.86  5160.3 1961.81  5177.8 1965.72
  5192.7  1967.1  5219.7 1967.53  5240.7 1968.78  5327.7 1976.17  5360.1 1976.76
#Mann= 5 ,-1 , 0
  4482.1      .1       0  4713.5     .07       0  5017.3     .05       0
  5033.3     .07       0  5140.4      .1       0
Bank Sta=5017.3,5033.3
XS Rating Curve= 0 ,0
Exp/Cntr=0.3,0.1

Type RM Length L Ch R = 1 ,14964   ,464,464,464
BEGIN DESCRIPTION:
Fessenden Branch 32.0
END DESCRIPTION:
XS GIS Cut Line= 3
        1862125.       13974925.        1862225.       13974525.
      1861925.01     13973975.01
#Sta/Elev= 30
  4588.1 1981.86  4639.6 1977.67    4686 1969.36  4711.8 1965.71  4722.1 1963.02
  4729.8 1959.32    4735 1958.15  4742.7 1954.81  4763.3  1949.9  4771.1 1949.25
  4866.4 1949.02  4977.2 1950.12  4990.1 1949.28  4997.8 1946.91  5003.3 1946.91
  5008.5 1944.66  5014.2 1944.81  5015.2 1942.88  5015.7 1942.38  5031.2 1942.88
    5036 1944.38    5046 1944.92  5161.3 1944.99  5205.4 1951.43  5261.8 1954.73
  5324.6  1957.2  5411.9 1966.35  5471.7 1967.83  5575.2 1974.62  5626.9 1976.64
#Mann= 5 ,-1 , 0
  4588.1      .1       0    4686     .07       0  5015.2     .05       0
  5031.2     .07       0  5261.8      .1       0
Bank Sta=5015.2,5031.2
XS Rating Curve= 0 ,0
Exp/Cntr=0.3,0.1

Type RM Length L Ch R = 1 ,14500   ,370,370,370
BEGIN DESCRIPTION:
Fessenden Branch 31.0
END DESCRIPTION:
XS GIS Cut Line= 3
        1862675.     13974675.02        1862675.       13974475.
      1862325.03     13973975.04
#Sta/Elev= 30
  4795.3 1991.77  4855.3 1990.76  4895.3  1986.4  4907.9 1983.29  4915.3 1980.45
  4925.3 1974.49  4935.3 1969.88  4945.3    1962  4955.3 1956.38  4984.7 1937.83
  4985.2 1937.33  5000.9 1937.83  5002.7 1938.65  5017.6 1939.35  5031.9  1943.4
  5074.2 1944.51  5089.1 1945.95  5117.4 1947.18  5190.2 1946.57  5202.8  1947.2
  5246.9 1945.65  5261.7 1947.58  5419.5 1952.57  5470.1 1955.35  5511.9 1959.36
  5547.7 1964.25  5583.4 1966.31  5592.1 1966.19  5598.2 1967.26  5605.6 1966.99
#Mann= 4 ,-1 , 0
  4795.3      .1       0  4907.9     .07       0  4984.7     .05       0
  5000.9     .07       0
Bank Sta=4984.7,5000.9
XS Rating Curve= 0 ,0
Exp/Cntr=0.3,0.1

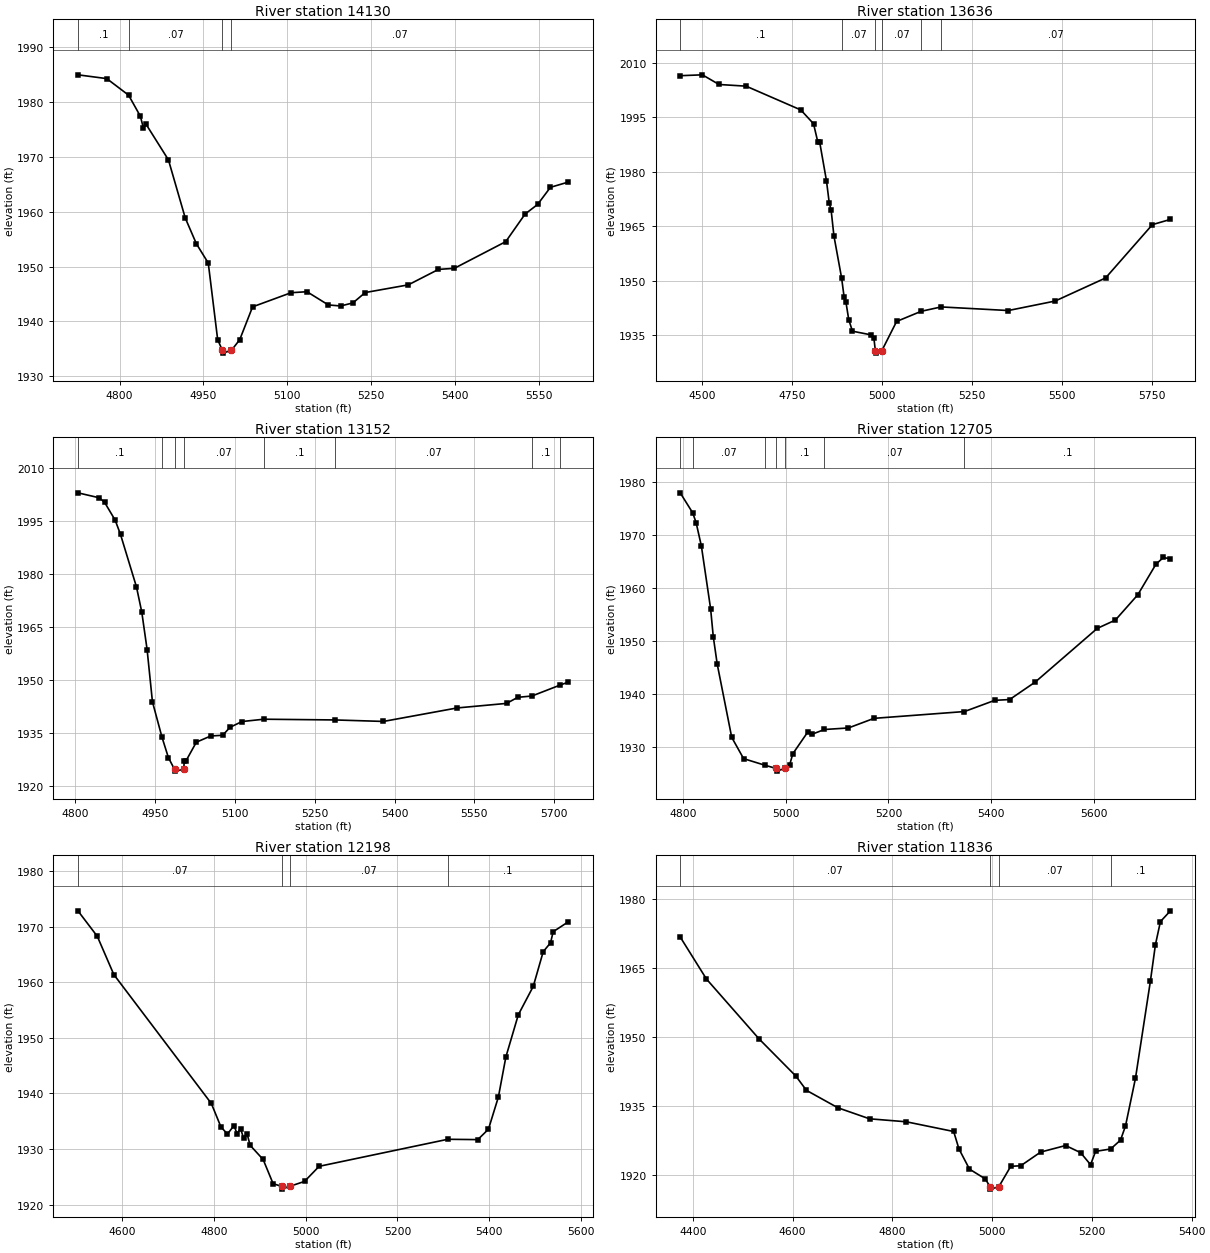
Type RM Length L Ch R = 1 ,14130   ,494,494,494
BEGIN DESCRIPTION:
Fessenden Branch 30.0
END DESCRIPTION:
XS GIS Cut Line= 3
      1862979.88     13974476.38      1862960.25     13974243.87
      1862374.99       13973975.
#Sta/Elev= 30
  4725.5 1984.96  4777.1 1984.27  4816.2 1981.25  4837.3  1977.4  4842.6  1975.3
  4847.6 1975.92  4887.5 1969.45  4917.6 1958.85  4937.6 1954.13  4958.8 1950.63
  4975.6 1936.68    4984  1934.7  4984.5  1934.2  5000.2  1934.7  5015.1 1936.65
  5038.1 1942.64    5107 1945.22  5135.5  1945.4  5173.7 1942.99  5195.7  1942.8
  5217.7 1943.36  5239.7 1945.25  5316.8 1946.65  5370.8 1949.47  5399.3 1949.67
  5491.2 1954.53  5525.9 1959.57  5548.2 1961.31  5571.2 1964.44  5602.9 1965.39
#Mann= 4 ,-1 , 0
  4725.5      .1       0  4816.2     .07       0    4984     .05       0
  5000.2     .07       0
Bank Sta=4984,5000.2
XS Rating Curve= 0 ,0
Exp/Cntr=0.3,0.1

Type RM Length L Ch R = 1 ,13636   ,484,484,484
BEGIN DESCRIPTION:
Fessenden Branch 29.0
END DESCRIPTION:
XS GIS Cut Line= 4
      1863725.87     13973926.57      1863346.61      13973867.9
        1863175.       13973825.      1862374.96       13973825.
#Sta/Elev= 30
  4439.4 2006.46    4501  2006.7  4547.2 2004.04  4622.4 2003.58  4774.2 1997.03
  4809.5 1993.23  4821.5 1988.16  4826.6 1988.16  4845.4 1977.53  4853.2 1971.37
  4858.3 1969.48  4866.1 1962.36  4887.5 1950.72  4894.4  1945.5  4899.6 1944.03
  4907.3 1939.25  4917.6 1936.11  4969.1  1935.1  4976.9 1934.32  4981.3 1930.57
  4981.8 1930.07  4998.2 1930.57  5040.1 1938.79  5108.4 1941.59  5163.8 1942.79
  5350.1  1941.8  5480.1 1944.41  5620.1 1950.76  5750.1 1965.45  5800.1 1966.89
#Mann= 6 ,-1 , 0
  4439.4      .1       0  4887.5     .07       0  4981.3     .05       0
  4998.2     .07       0  5108.4      .1       0  5163.8     .07       0
Bank Sta=4981.3,4998.2
XS Rating Curve= 0 ,0
Exp/Cntr=0.3,0.1

Type RM Length L Ch R = 1 ,13152   ,447,447,447
BEGIN DESCRIPTION:
Fessenden Branch 28.0
END DESCRIPTION:
XS GIS Cut Line= 3
        1863375.       13973375.        1863175.       13973375.
      1862575.01     13973774.99
#Sta/Elev= 30
  4805.1 2002.89  4845.1 2001.49  4855.1 2000.23  4875.1 1995.15  4885.1 1991.13
  4915.1 1976.29  4925.1 1969.16  4935.1 1958.56  4945.1 1943.82    4963 1933.82
  4975.1 1928.02  4986.6  1924.7  4987.1  1924.2  5003.6  1924.7  5005.1 1927.09
  5008.1 1927.09  5027.6 1932.38  5054.7 1934.14  5077.2 1934.34  5090.7 1936.57
  5113.3 1938.22  5154.5 1938.88  5288.5 1938.67  5379.2 1938.25  5517.4 1942.06
  5610.5 1943.35  5631.6 1945.07  5658.2 1945.44  5710.6  1948.5  5726.2 1949.35
#Mann= 8 ,-1 , 0
  4805.1      .1       0    4963     .07       0  4986.6     .05       0
  5003.6     .07       0  5154.5      .1       0  5288.5     .07       0
  5658.2      .1       0  5710.6     .07       0
Bank Sta=4986.6,5003.6
XS Rating Curve= 0 ,0
Exp/Cntr=0.3,0.1

Type RM Length L Ch R = 1 ,12705   ,507,507,507
BEGIN DESCRIPTION:
Fessenden Branch 27.0
END DESCRIPTION:
XS GIS Cut Line= 3
      1863075.03     13973024.99        1862875.       13973075.
      1862274.99     13973525.01
#Sta/Elev= 30
  4793.8 1977.88  4818.2 1974.11  4824.8 1972.28  4835.1 1967.87  4853.1 1956.07
  4858.3 1950.81    4866 1945.63  4894.3 1931.83  4917.5 1927.82  4958.4  1926.6
  4981.2 1925.97  4981.7 1925.47  4998.2 1925.97  5007.3 1926.65  5013.5 1928.75
  5042.7 1932.84    5050 1932.38  5075.1 1933.31  5121.9  1933.6  5171.9 1935.41
  5348.3 1936.69  5407.3  1938.8  5436.4 1938.95  5486.4 1942.25  5607.3 1952.35
  5642.7 1953.92  5686.4 1958.68  5721.9 1964.45  5736.4 1965.71    5750 1965.44
#Mann= 7 ,-1 , 0
  4793.8      .1       0  4818.2     .07       0  4958.4      .1       0
  4981.2     .05       0  4998.2      .1       0  5075.1     .07       0
  5348.3      .1       0
Bank Sta=4981.2,4998.2
XS Rating Curve= 0 ,0
Exp/Cntr=0.3,0.1

Type RM Length L Ch R = 1 ,12198   ,362,362,362
BEGIN DESCRIPTION:
Fessenden Branch 26.0
END DESCRIPTION:
XS GIS Cut Line= 3
        1862875.       13972475.      1862502.83     13972802.21
      1861974.98     13973025.01
#Sta/Elev= 30
  4503.5 1972.91  4545.7 1968.32  4581.8 1961.42  4794.3  1938.2  4815.2 1933.98
  4829.4 1932.69  4843.6 1934.22  4850.3 1932.78  4857.9 1933.68  4864.5 1931.99
  4872.1 1932.78  4878.8 1930.67  4907.2 1928.11    4929 1923.74    4948 1923.27
  4948.5 1922.77  4965.2 1923.27  4997.4 1924.16  5029.3 1926.88  5309.7 1931.75
  5375.1 1931.69  5398.3 1933.56    5420 1939.37  5436.3 1946.58  5463.4 1954.18
    5496  1959.3  5517.7 1965.55  5533.7 1967.15  5539.4 1969.15    5572 1970.91
#Mann= 4 ,-1 , 0
  4503.5     .07       0    4948     .05       0  4965.2     .07       0
  5309.7      .1       0
Bank Sta=4948,4965.2
XS Rating Curve= 0 ,0
Exp/Cntr=0.3,0.1

Type RM Length L Ch R = 1 ,11836   ,485,485,485
BEGIN DESCRIPTION:
Fessenden Branch 25.0
END DESCRIPTION:
XS GIS Cut Line= 3
      1862825.02     13972374.99        1862225.       13972575.
      1861874.97       13972575.
#Sta/Elev= 30
  4374.9 1971.77  4427.6 1962.62    4533 1949.61  4606.8 1941.52  4627.9 1938.43
  4691.1 1934.63  4754.4 1932.24  4828.2 1931.59    4923 1929.48  4933.6 1925.69
  4954.7  1921.3  4986.3 1919.18  4996.1 1917.45  4996.6 1916.95  5013.4 1917.45
  5037.4 1921.91  5057.4 1922.03  5097.4 1925.01  5147.4 1926.43  5177.4 1924.88
  5197.4 1922.26  5207.4 1925.16  5237.7 1925.68  5257.4 1927.61  5267.4 1930.68
  5287.4 1941.06  5317.4 1962.25  5327.4 1970.11  5337.4 1975.12  5357.4 1977.46
#Mann= 4 ,-1 , 0
  4374.9     .07       0  4996.1     .05       0  5013.4     .07       0
  5237.7      .1       0
#XS Ineff= 2 , 0
                         5143.46         1926.21
Permanent Ineff=
       F       F
Bank Sta=4996.1,5013.4
XS Rating Curve= 0 ,0
Exp/Cntr=0.3,0.1