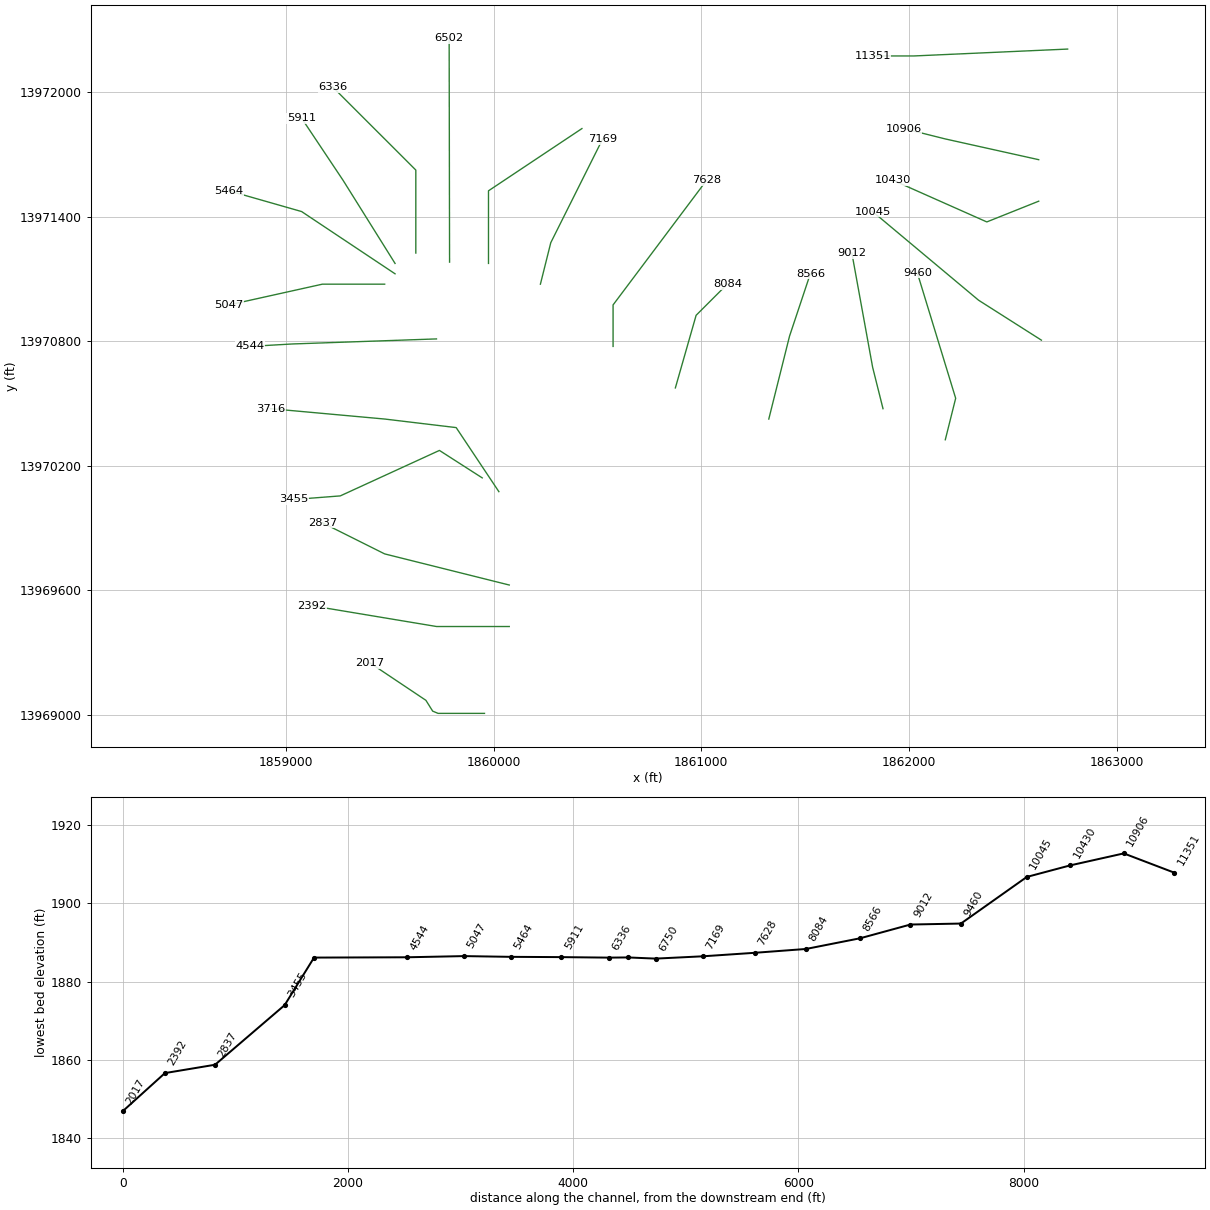
HEC-RAS study Fessenden Branch.prj: Fessenden Branch Base Level Engineering

--- Fessenden Branch.g01 (geometry) --- (continued)

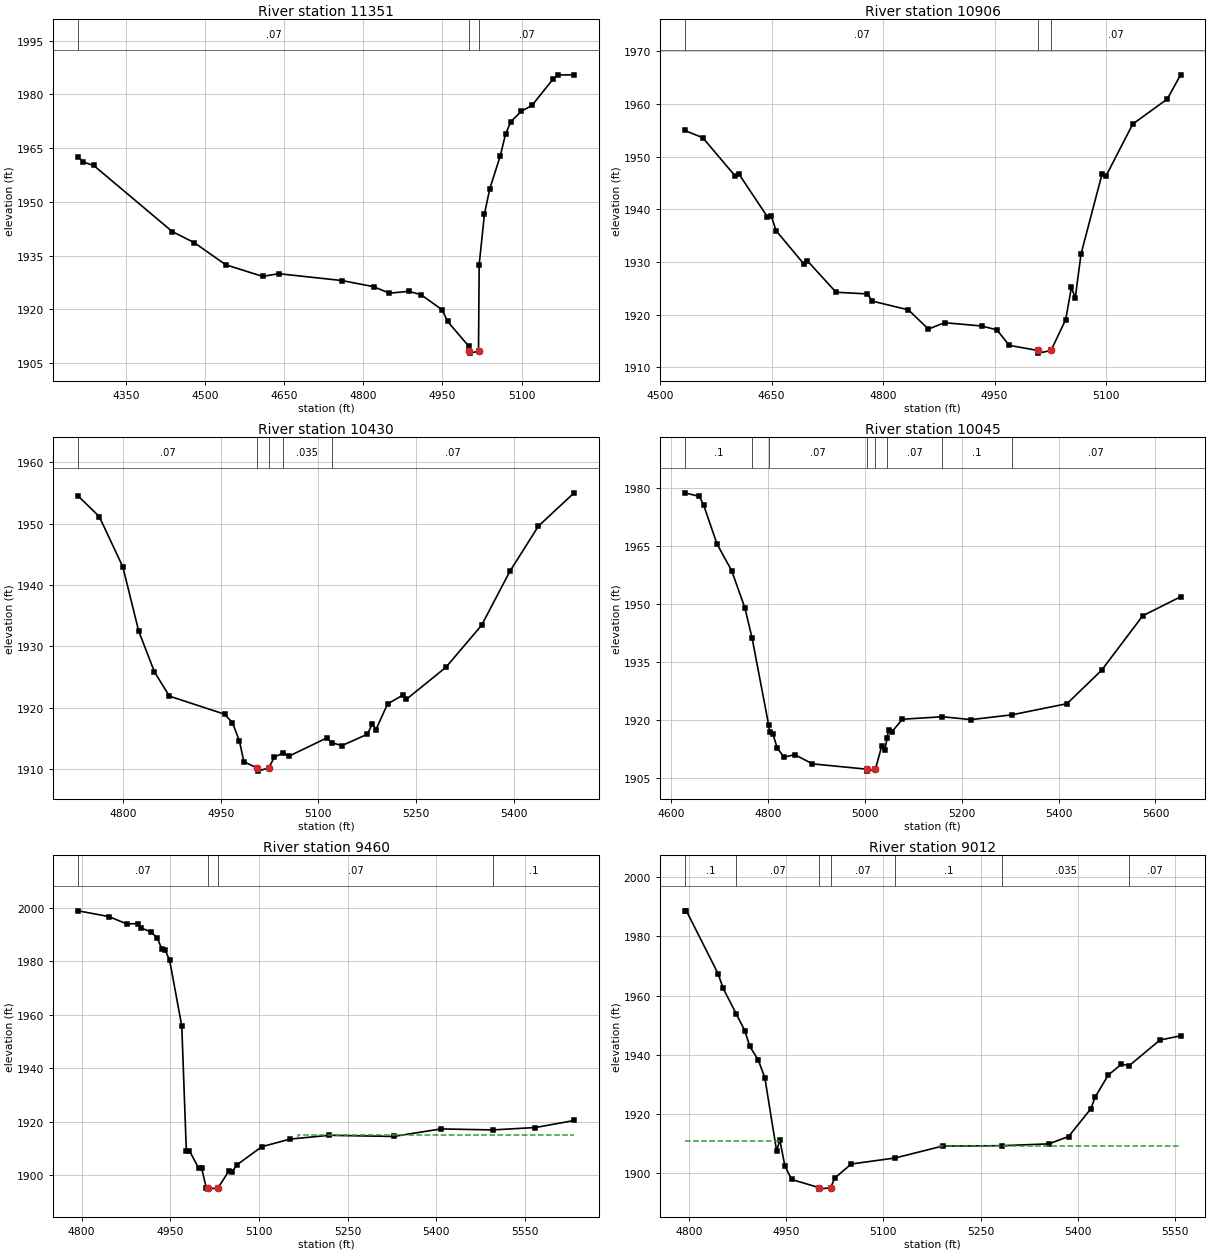
Type RM Length L Ch R = 1 ,11351   ,445,445,445
BEGIN DESCRIPTION:
Fessenden Branch 24.0
END DESCRIPTION:
XS GIS Cut Line= 3
      1862764.27     13972208.15        1862025.       13972175.
      1861825.01       13972175.
#Sta/Elev= 30
  4259.6 1962.61  4268.9 1961.13  4288.9 1960.16  4437.8 1941.74  4479.1 1938.67
  4539.2 1932.47  4609.2 1929.22  4639.3 1929.98  4759.4 1928.07  4819.4 1926.36
  4849.5 1924.54  4886.2 1925.07  4909.5 1924.11  4949.6 1919.89  4959.6 1916.67
  4999.6 1909.81    5001 1908.33  5001.5 1907.83  5018.3 1908.33  5019.6 1932.53
  5029.6 1946.62  5039.6 1953.62  5059.6 1962.83  5069.6 1968.93  5079.6 1972.36
  5099.6  1975.3  5119.6 1976.89  5159.6 1984.23  5169.6  1985.4  5199.6 1985.43
#Mann= 3 ,-1 , 0
  4259.6     .07       0    5001     .05       0  5018.3     .07       0
Bank Sta=5001,5018.3
XS Rating Curve= 0 ,0
Exp/Cntr=0.3,0.1

Type RM Length L Ch R = 1 ,10906   ,476,476,476
BEGIN DESCRIPTION:
Fessenden Branch 23.0
END DESCRIPTION:
XS GIS Cut Line= 3
      1862624.96     13971675.01        1862175.       13971775.
      1861974.99       13971825.
#Sta/Elev= 30
  4533.1 1954.94  4557.4 1953.58  4600.9 1946.33    4606 1946.69  4644.5 1938.55
  4649.6 1938.75    4656 1935.94  4693.1 1929.67  4698.2 1930.21  4736.7 1924.26
  4778.9 1923.94  4785.3 1922.58    4834 1920.92  4860.9 1917.27  4882.6 1918.48
  4932.6 1917.86  4953.1 1917.12  4969.7 1914.18  5008.5 1913.21    5009 1912.71
  5025.9 1913.21  5045.6 1919.07  5053.3 1925.16  5058.5 1923.21  5066.2  1931.5
  5094.5 1946.68  5099.7 1946.27  5135.8 1956.16  5182.2  1960.9  5200.2  1965.5
#Mann= 3 ,-1 , 0
  4533.1     .07       0  5008.5     .05       0  5025.9     .07       0
Bank Sta=5008.5,5025.9
XS Rating Curve= 0 ,0
Exp/Cntr=0.3,0.1

Type RM Length L Ch R = 1 ,10430   ,385,385,385
BEGIN DESCRIPTION:
Fessenden Branch 22.0
END DESCRIPTION:
XS GIS Cut Line= 3
      1862624.96     13971474.99        1862375.       13971375.
      1861924.96     13971575.02
#Sta/Elev= 30
  4731.2  1954.5  4763.5 1951.16  4799.8 1942.94  4824.1 1932.48  4848.3 1925.83
  4871.2 1921.88    4956 1918.93  4968.1 1917.54  4978.9 1914.52  4985.6  1911.2
  5006.1 1910.15  5006.6 1909.65  5023.5 1910.15  5032.6 1911.93  5045.2 1912.58
  5055.1  1912.1  5113.3 1915.08  5120.3 1914.28  5136.5 1913.82  5175.5 1915.68
    5183 1917.38  5188.5 1916.43  5206.3  1920.6  5229.5 1922.03    5235 1921.34
  5295.9 1926.58  5350.6 1933.41  5394.4 1942.27  5438.1 1949.61  5492.9 1955.03
#Mann= 5 ,-1 , 0
  4731.2     .07       0  5006.1     .05       0  5023.5     .07       0
  5045.2    .035       0  5120.3     .07       0
Bank Sta=5006.1,5023.5
XS Rating Curve= 0 ,0
Exp/Cntr=0.3,0.1

Type RM Length L Ch R = 1 ,10045   ,585,585,585
BEGIN DESCRIPTION:
Fessenden Branch 21.0
END DESCRIPTION:
XS GIS Cut Line= 3
      1862637.81     13970805.19      1862335.12     13970997.86
      1861825.03     13971424.98
#Sta/Elev= 30
  4627.8 1978.71  4658.1 1977.79  4666.7 1975.64  4694.5 1965.48  4724.9 1958.55
    4752 1948.98  4767.1 1941.06  4801.3 1918.59  4803.7  1916.8  4809.6 1916.42
  4818.9 1912.71  4832.6 1910.33  4855.3 1910.95  4891.7 1908.58    5004  1907.2
  5004.5  1906.7  5021.7  1907.2  5034.5 1913.08  5041.1  1912.1  5045.6 1915.16
  5048.8 1917.34  5055.4 1916.84  5077.5 1920.13  5159.7 1920.77  5219.3 1920.03
  5303.6 1921.27  5417.2 1924.15  5488.6 1932.78  5573.7  1946.9  5651.9 1951.82
#Mann= 8 ,-1 , 0
  4627.8      .1       0  4767.1     .07       0  4801.3     .07       0
    5004     .05       0  5021.7     .07       0  5045.6     .07       0
  5159.7      .1       0  5303.6     .07       0
Bank Sta=5004,5021.7
XS Rating Curve= 0 ,0
Exp/Cntr=0.3,0.1

Type RM Length L Ch R = 1 ,9460    ,448,448,448
BEGIN DESCRIPTION:
Fessenden Branch 20.0
END DESCRIPTION:
XS GIS Cut Line= 3
      1862175.01     13970325.03        1862225.       13970525.
      1862040.06     13971130.25
#Sta/Elev= 30
  4794.4 1998.86  4845.9 1996.73  4876.8 1993.95  4894.9 1994.09    4900 1992.52
  4918.1 1990.93  4928.4 1988.58  4936.1 1984.46  4941.3 1984.15    4949 1980.47
  4969.6 1955.77  4977.3 1909.13  4982.5 1909.18  4997.9  1902.7  5003.1  1902.7
    5011 1895.38  5013.3  1895.3  5013.8  1894.8    5031  1895.3  5049.7  1901.7
  5054.9 1901.39  5063.3 1903.95  5105.1 1910.68  5153.3 1913.52  5218.9 1914.92
  5327.8  1914.5  5408.3 1917.31  5495.6 1916.94  5567.8 1917.83  5633.4 1920.47
#Mann= 4 ,-1 , 0
  4794.4     .07       0  5013.3     .05       0    5031     .07       0
  5495.6      .1       0
#XS Ineff= 2 , 0
                         5165.83         1914.97
Permanent Ineff=
       F       F
Bank Sta=5013.3,5031
XS Rating Curve= 0 ,0
Exp/Cntr=0.3,0.1

Type RM Length L Ch R = 1 ,9012    ,446,446,446
BEGIN DESCRIPTION:
Fessenden Branch 19.0
END DESCRIPTION:
XS GIS Cut Line= 3
      1861875.01     13970474.97        1861825.       13970675.
        1861725.       13971225.
#Sta/Elev= 30
  4793.5 1988.68  4796.1 1988.68  4845.1 1967.39  4852.8  1962.5  4872.9 1953.89
  4886.3 1948.13    4894  1942.8  4906.9  1938.3  4917.2 1932.21  4935.3 1907.54
  4940.4 1911.06  4948.1 1902.39  4958.5 1897.82  5000.9 1895.05  5001.4 1894.55
  5018.7 1895.05  5025.1  1898.3  5050.5 1903.05  5118.4 1905.09  5191.5 1909.12
  5282.8 1909.24  5355.4 1909.86  5385.9 1912.35  5420.2 1921.73  5426.6 1925.58
  5446.9 1933.09  5467.2 1936.78  5479.6 1936.35  5526.9 1944.99  5558.7  1946.4
#Mann= 7 ,-1 , 0
  4793.5      .1       0  4872.9     .07       0  5000.9     .05       0
  5018.7     .07       0  5118.4      .1       0  5282.8    .035       0
  5479.6     .07       0
#XS Ineff= 2 , 0
         4939.66 1910.66 5186.41         1909.22
Permanent Ineff=
       F       F
Bank Sta=5000.9,5018.7
XS Rating Curve= 0 ,0
Exp/Cntr=0.3,0.1

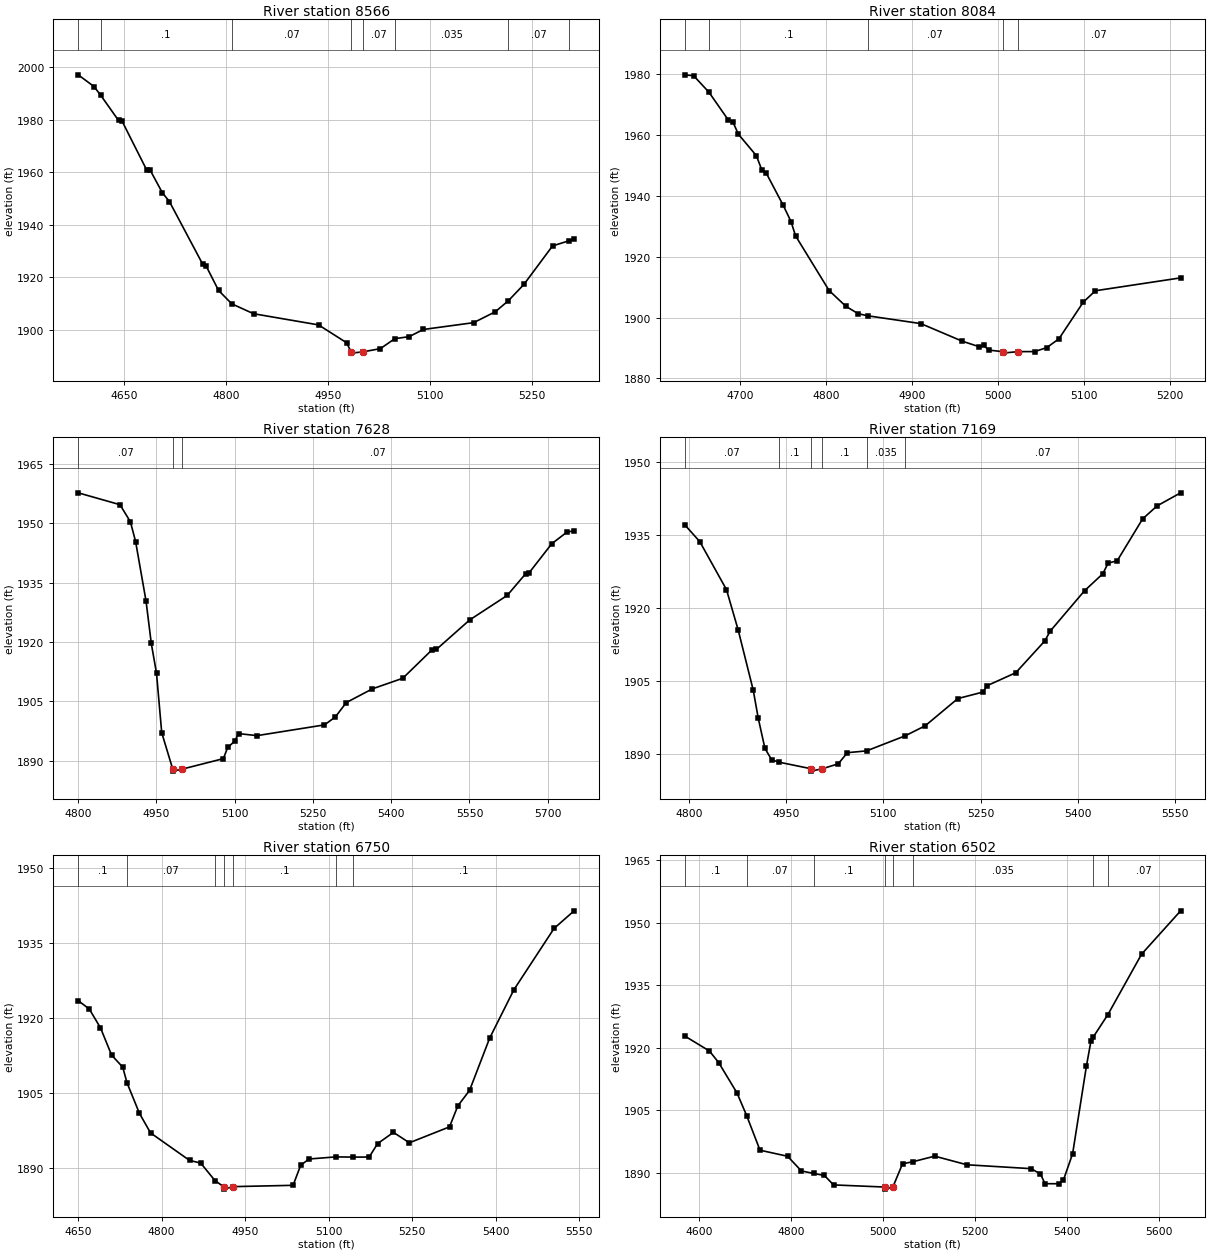
Type RM Length L Ch R = 1 ,8566    ,482,482,482
BEGIN DESCRIPTION:
Fessenden Branch 18.0
END DESCRIPTION:
XS GIS Cut Line= 3
      1861324.99     13970424.98        1861425.       13970825.
      1861525.01     13971125.04
#Sta/Elev= 30
  4583.1 1997.02  4606.3 1992.57    4616 1989.29  4642.4 1979.63  4647.5 1979.41
  4683.6 1960.84  4688.8 1960.73  4706.8 1952.09  4717.1 1948.77  4766.1 1924.86
  4771.2 1924.15  4789.3 1914.92  4808.8 1909.81  4840.8 1906.05  4936.2  1901.8
  4977.4 1895.01    4984 1891.55  4984.5 1891.05  5001.8 1891.55  5027.1 1892.76
  5048.3 1896.56  5069.2 1897.31  5090.3 1900.06  5164.1 1902.65  5195.7 1906.77
  5215.1 1910.99  5237.9 1917.19    5280 1931.86  5304.9  1933.9  5311.7 1934.38
#Mann= 8 ,-1 , 0
  4583.1     .07       0    4616      .1       0  4808.8     .07       0
    4984     .05       0  5001.8     .07       0  5048.3    .035       0
  5215.1     .07       0  5304.9    .035       0
Bank Sta=4984,5001.8
XS Rating Curve= 0 ,0
Exp/Cntr=0.3,0.1

Type RM Length L Ch R = 1 ,8084    ,456,456,456
BEGIN DESCRIPTION:
Fessenden Branch 17.0
END DESCRIPTION:
XS GIS Cut Line= 3
        1860875.     13970575.01        1860975.       13970925.
      1861124.98     13971074.98
#Sta/Elev= 30
  4635.9 1979.72  4646.3 1979.41  4664.1 1973.98  4686.6 1964.85  4691.8 1964.25
  4698.3 1960.19  4719.1 1953.17  4725.6 1948.38  4730.8 1947.33  4750.3 1936.86
  4759.4  1931.5  4764.6 1926.85  4803.6 1908.88  4823.1 1903.68  4837.4 1901.27
  4848.3 1900.58  4910.2 1898.01  4958.3 1892.23  4977.8 1890.43    4983 1890.83
  4989.5 1889.29  5005.1 1888.81  5005.6 1888.31  5022.9 1888.81  5042.3 1888.81
  5056.5 1890.12  5070.6 1893.01  5098.9 1905.06    5113  1908.8    5212 1913.03
#Mann= 5 ,-1 , 0
  4635.9     .07       0  4664.1      .1       0  4848.3     .07       0
  5005.1     .05       0  5022.9     .07       0
Bank Sta=5005.1,5022.9
XS Rating Curve= 0 ,0
Exp/Cntr=0.3,0.1

Type RM Length L Ch R = 1 ,7628    ,459,459,459
BEGIN DESCRIPTION:
Fessenden Branch 16.0
END DESCRIPTION:
XS GIS Cut Line= 3
        1860575.     13970775.05        1860575.       13970975.
      1861025.03     13971575.04
#Sta/Elev= 30
  4800.4 1957.73  4880.4 1954.73  4900.4  1950.4  4910.4 1945.37  4930.4 1930.31
  4940.4 1919.63  4950.4 1912.08  4960.4 1897.05  4981.5 1887.83    4982 1887.33
  4999.3 1887.83  5078.5 1890.49  5086.8 1893.33  5100.4 1894.91  5107.6 1896.82
  5143.1 1896.31  5272.2 1899.03  5293.1 1901.04  5313.9 1904.67  5363.9 1908.14
  5422.2 1910.82  5478.5 1918.05  5486.8 1918.14  5550.4 1925.58  5622.2 1931.77
  5657.6 1937.26  5663.9 1937.44  5707.6 1944.85  5736.8  1947.8  5750.4 1948.12
#Mann= 3 ,-1 , 0
  4800.4     .07       0  4981.5     .05       0  4999.3     .07       0
Bank Sta=4981.5,4999.3
XS Rating Curve= 0 ,0
Exp/Cntr=0.3,0.1

Type RM Length L Ch R = 1 ,7169    ,419,419,419
BEGIN DESCRIPTION:
Fessenden Branch 15.0
END DESCRIPTION:
XS GIS Cut Line= 3
        1860225.       13971075.        1860275.       13971275.
      1860525.01     13971775.02
#Sta/Elev= 30
  4793.4 1937.06  4816.6 1933.61  4857.8 1923.74  4875.9 1915.43  4899.1 1903.08
  4906.8 1897.33  4917.1 1891.13  4927.4 1888.79  4938.2  1888.3    4988 1886.94
  4988.5 1886.44  5005.9 1886.94  5030.3 1887.94  5044.3 1890.23    5074  1890.6
  5133.5 1893.69  5164.5 1895.76  5214.8 1901.35  5253.9  1902.7  5259.5 1903.97
  5304.2 1906.66  5348.9 1913.18  5357.3  1915.2  5410.4 1923.52  5438.4 1926.98
  5446.8 1929.19  5460.7 1929.66  5499.9 1938.26  5522.2 1940.94  5558.6 1943.63
#Mann= 6 ,-1 , 0
  4793.4     .07       0  4938.2      .1       0    4988     .05       0
  5005.9      .1       0    5074    .035       0  5133.5     .07       0
Bank Sta=4988,5005.9
XS Rating Curve= 0 ,0
Exp/Cntr=0.3,0.1

Type RM Length L Ch R = 1 ,6750    ,248,248,248
BEGIN DESCRIPTION:
Fessenden Branch 14.0
END DESCRIPTION:
XS GIS Cut Line= 3
        1859975.     13971175.02        1859975.       13971525.
      1860424.99     13971824.99
#Sta/Elev= 30
  4650.3 1923.52  4670.3 1921.82  4690.3 1918.08  4710.3 1912.63  4730.3 1910.22
    4738 1907.08  4760.3 1900.99  4780.3 1897.08  4850.3 1891.59  4870.3 1891.06
  4895.9 1887.57  4911.3 1886.35  4911.8 1885.85  4929.2 1886.35  5036.3 1886.61
  5049.9 1890.61  5064.9 1891.87  5112.9 1892.29  5144.1 1892.25    5173 1892.26
  5188.1 1894.94  5216.6 1897.19  5245.2 1895.11  5317.3 1898.29  5332.3  1902.5
  5353.3 1905.57  5389.4 1916.02  5432.9 1925.68  5505.1 1937.94  5541.1 1941.46
#Mann= 7 ,-1 , 0
  4650.3      .1       0    4738     .07       0  4895.9      .1       0
  4911.3     .05       0  4929.2      .1       0  5112.9     .07       0
  5144.1      .1       0
Bank Sta=4911.3,4929.2
XS Rating Curve= 0 ,0
Exp/Cntr=0.3,0.1

Type RM Length L Ch R = 1 ,6502    ,166,166,166
BEGIN DESCRIPTION:
Mapping XS 37d3fa8d
END DESCRIPTION:
XS GIS Cut Line= 2
      1859787.55     13971181.28      1859785.53     13972259.87
#Sta/Elev= 30
  4569.1 1922.82  4622.8 1919.23  4642.8 1916.47  4682.8 1909.18  4703.7 1903.78
  4732.8 1895.47  4792.8 1894.02  4822.8 1890.51  4849.4  1889.9  4872.8 1889.43
  4892.8 1887.16  5003.9 1886.65  5004.4 1886.15  5021.8 1886.65  5042.8 1892.21
    5066 1892.73  5112.8 1894.05  5182.8 1891.98  5322.8 1891.05  5342.8 1889.76
  5352.8 1887.45  5382.8 1887.44  5392.8 1888.32  5412.8 1894.64  5442.8 1915.61
  5452.8  1921.7  5457.8  1922.6  5489.5 1927.95  5562.8 1942.42  5647.7  1952.8
#Mann= 8 ,-1 , 0
  4569.1      .1       0  4703.7     .07       0  4849.4      .1       0
  5003.9     .05       0  5021.8      .1       0    5066    .035       0
  5457.8      .1       0  5489.5     .07       0
Bank Sta=5003.9,5021.8
XS Rating Curve= 0 ,0
Exp/Cntr=0.3,0.1

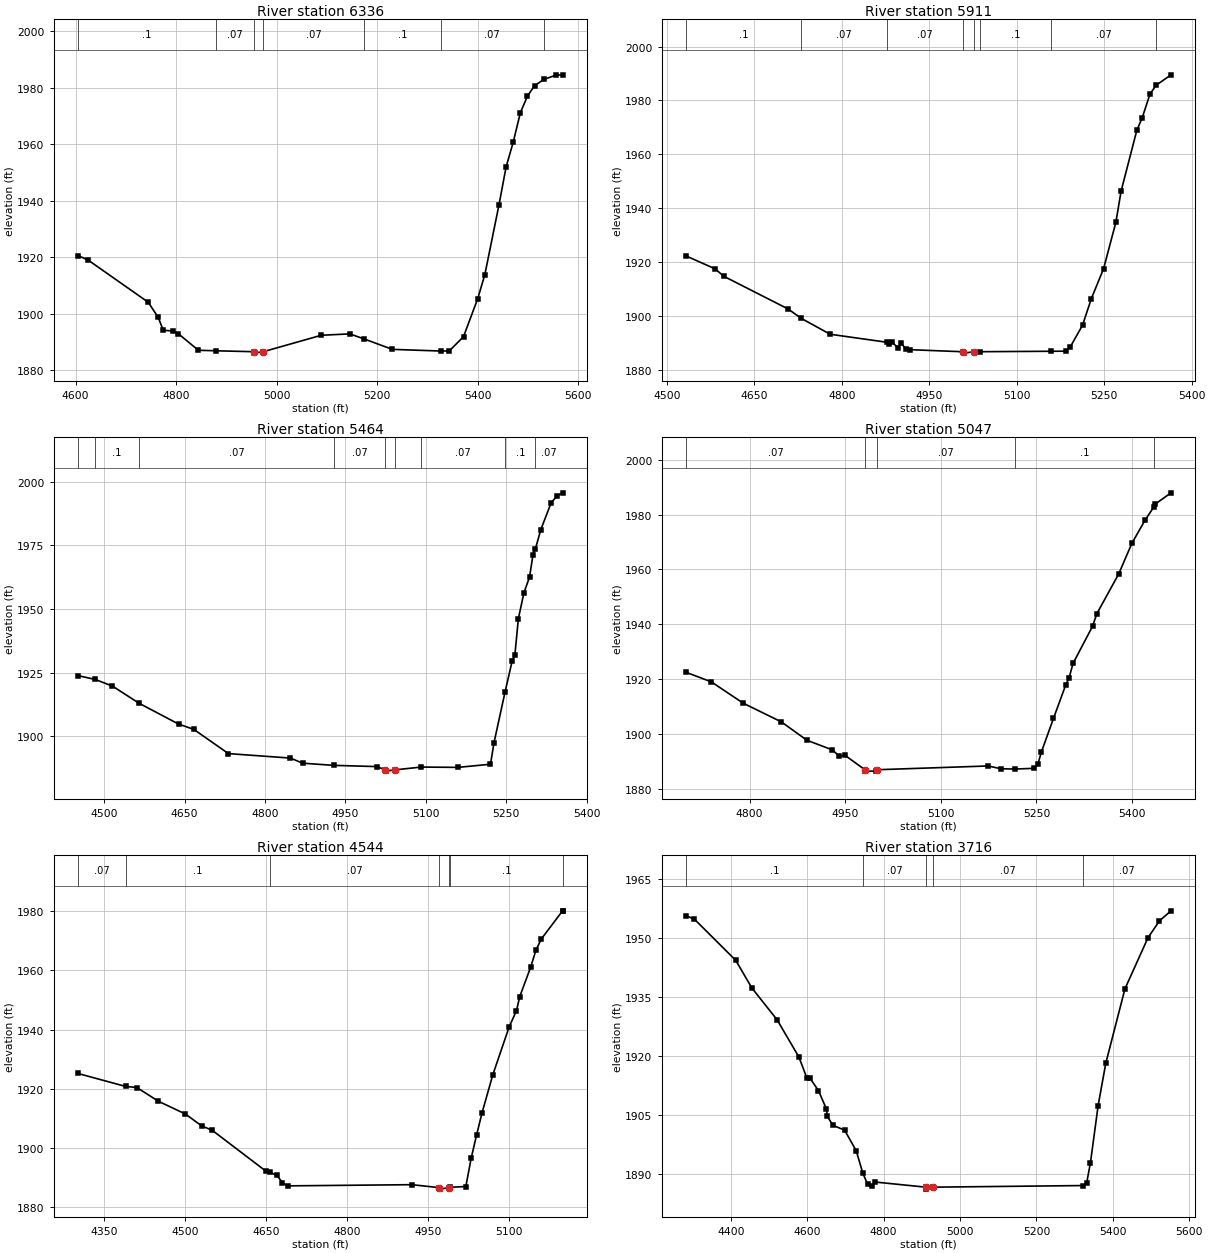
Type RM Length L Ch R = 1 ,6336    ,425,425,425
BEGIN DESCRIPTION:
Fessenden Branch 13.0
END DESCRIPTION:
XS GIS Cut Line= 3
        1859625.     13971225.02        1859625.       13971625.
      1859224.97     13972025.03
#Sta/Elev= 30
  4604.3 1920.66  4624.3 1919.12  4744.3 1904.14  4764.3 1898.79  4774.3 1894.19
  4794.3 1893.93  4804.3 1892.98  4844.3 1887.11  4879.4 1886.93  4955.3  1886.6
  4955.8  1886.1  4973.3  1886.6  5089.1 1892.43  5145.7 1892.91  5173.5 1891.16
  5230.5 1887.43  5326.7 1886.84  5343.7 1886.88    5372 1891.94  5400.3  1905.4
  5414.4 1913.87  5442.7 1938.71  5456.8 1952.05    5471 1960.86  5485.1  1971.2
  5499.3 1977.14  5513.4 1980.76  5531.5 1982.99  5555.8 1984.53    5570 1984.64
#Mann= 7 ,-1 , 0
  4604.3      .1       0  4879.4     .07       0  4955.3     .05       0
  4973.3     .07       0  5173.5      .1       0  5326.7     .07       0
  5531.5      .1       0
Bank Sta=4955.3,4973.3
XS Rating Curve= 0 ,0
Exp/Cntr=0.3,0.1

Type RM Length L Ch R = 1 ,5911    ,447,447,447
BEGIN DESCRIPTION:
Fessenden Branch 12.0
END DESCRIPTION:
XS GIS Cut Line= 3
      1859524.99     13971175.01        1859275.       13971575.
      1859075.02     13971874.97
#Sta/Elev= 30
  4532.4 1922.33  4582.5 1917.51  4597.8 1914.71  4707.5 1902.65  4730.7 1899.09
    4780 1893.23  4877.1 1890.27  4880.9  1889.6  4886.7  1890.2  4896.2 1888.21
  4902.1 1889.86  4909.7 1887.73  4917.4 1887.51  5008.5 1886.73    5009 1886.23
  5026.7 1886.73  5036.7 1886.76    5159 1886.92  5184.4 1886.95  5191.9 1888.57
  5212.9 1896.63  5227.9 1906.43    5249 1917.61    5270 1934.78    5279 1946.37
    5306 1968.95  5315.1 1973.49  5328.6 1982.42  5339.5 1985.69  5364.6 1989.49
#Mann= 8 ,-1 , 0
  4532.4      .1       0  4730.7     .07       0  4877.1     .07       0
  5008.5     .05       0  5026.7     .07       0  5036.7      .1       0
    5159     .07       0  5339.5      .1       0
Bank Sta=5008.5,5026.7
XS Rating Curve= 0 ,0
Exp/Cntr=0.3,0.1

Type RM Length L Ch R = 1 ,5464    ,417,417,417
BEGIN DESCRIPTION:
Fessenden Branch 11.0
END DESCRIPTION:
XS GIS Cut Line= 3
      1859524.97     13971125.02        1859075.       13971425.
        1858725.       13971525.
#Sta/Elev= 30
  4450.9 1923.81    4483 1922.31  4515.5 1919.69  4565.2 1912.94  4638.7 1904.79
  4667.2 1902.69  4731.8 1893.18  4847.5 1891.42    4870 1889.42  4928.6 1888.56
  5008.6 1888.08  5024.2  1886.8  5024.7  1886.3  5042.4  1886.8  5091.5  1887.9
  5159.4 1887.77  5220.5    1889    5227 1897.42  5247.6 1917.33  5260.8 1929.44
    5266 1931.98  5272.5  1946.2  5282.9 1956.36  5293.3 1962.49  5299.8 1971.32
  5304.4 1973.62  5314.1 1980.98  5333.6 1991.65  5345.3 1994.51  5355.7 1995.56
#Mann= 9 ,-1 , 0
  4450.9     .07       0    4483      .1       0  4565.2     .07       0
  4928.6     .07       0  5024.2     .05       0  5042.4     .07       0
  5091.5     .07       0  5247.6      .1       0  5304.4     .07       0
Bank Sta=5024.2,5042.4
XS Rating Curve= 0 ,0
Exp/Cntr=0.3,0.1

Type RM Length L Ch R = 1 ,5047    ,503,503,503
BEGIN DESCRIPTION:
Fessenden Branch 10.0
END DESCRIPTION:
XS GIS Cut Line= 3
        1859475.       13971075.        1859175.       13971075.
      1858724.98       13970975.
#Sta/Elev= 30
    4700 1922.53    4740 1919.02    4790 1911.25    4850 1904.41    4890 1897.73
    4930 1894.21    4940 1892.04    4950 1892.19  4980.9 1886.99  4981.4 1886.49
  4998.6 1886.49  4999.1 1886.99  5174.1 1888.37  5194.6 1887.34  5216.8 1887.25
  5245.9 1887.51  5252.3 1889.06  5257.4 1893.28  5276.6 1905.68  5295.8 1917.86
  5300.9 1920.29  5307.3 1925.72  5338.1 1939.37  5344.5 1943.78    5379 1958.38
  5399.5 1969.45    5420 1977.84    5434 1982.73  5436.6 1983.85    5461  1987.9
#Mann= 5 ,-1 , 0
    4700     .07       0  4980.9     .05       0  4999.1     .07       0
  5216.8      .1       0    5434     .07       0
Bank Sta=4980.9,4999.1
XS Rating Curve= 0 ,0
Exp/Cntr=0.3,0.1

Type RM Length L Ch R = 1 ,4544    ,828,828,828
BEGIN DESCRIPTION:
Fessenden Branch 9.0
END DESCRIPTION:
XS GIS Cut Line= 3
      1859724.49     13970811.16      1859030.95     13970786.82
      1858824.96       13970775.
#Sta/Elev= 30
  4300.5 1925.21  4389.1 1920.83  4410.1 1920.46  4450.1 1915.82  4500.1 1911.53
  4530.1 1907.55  4550.1 1906.01  4650.2 1892.16  4657.1 1891.85  4670.2  1890.8
  4680.2 1888.38  4690.2 1887.29  4920.4 1887.69  4971.3 1886.69  4971.8 1886.19
  4989.5 1886.69  4991.6 1886.81  5020.5 1887.07  5030.5 1896.68  5040.5 1904.49
  5050.5 1911.87  5070.5 1924.71  5100.6 1940.75  5114.5 1946.42  5120.6 1951.14
  5140.7    1961  5150.7 1966.84  5160.7 1970.59    5200 1980.05  5200.8 1980.05
#Mann= 7 ,-1 , 0
  4300.5     .07       0  4389.1      .1       0  4657.1     .07       0
  4971.3     .05       0  4989.5     .07       0  4991.6      .1       0
    5200     .07       0
Bank Sta=4971.3,4989.5
XS Rating Curve= 0 ,0
Exp/Cntr=0.3,0.1

Type RM Length L Ch R = 1 ,3716    ,261,261,261
BEGIN DESCRIPTION:
Fessenden Branch 8.0
END DESCRIPTION:
XS GIS Cut Line= 4
        1860025.       13970075.      1859819.36     13970383.74
        1859475.       13970425.      1858924.95       13970475.
#Sta/Elev= 30
  4282.1 1955.74  4304.6 1954.83  4412.8 1944.35  4454.9 1937.33    4521 1929.22
  4578.1 1919.74  4599.1 1914.36  4606.5 1914.44  4629.2 1911.21  4650.2 1906.49
  4652.5 1904.61  4667.5 1902.33  4697.7 1901.13    4728 1895.91  4745.6 1890.12
  4758.2  1887.3  4768.2 1887.02  4778.3 1887.91  4910.2 1886.61  4910.7 1886.11
  4928.4 1886.61  5322.1 1887.02  5331.2 1887.57  5341.3 1892.84  5361.4 1907.39
  5381.5  1918.2  5431.7 1937.13  5491.9 1950.11    5522 1954.42  5552.2 1956.96
#Mann= 5 ,-1 , 0
  4282.1      .1       0  4745.6     .07       0  4910.2     .05       0
  4928.4     .07       0  5322.1     .07       0
Bank Sta=4910.2,4928.4
XS Rating Curve= 0 ,0
Exp/Cntr=0.3,0.1

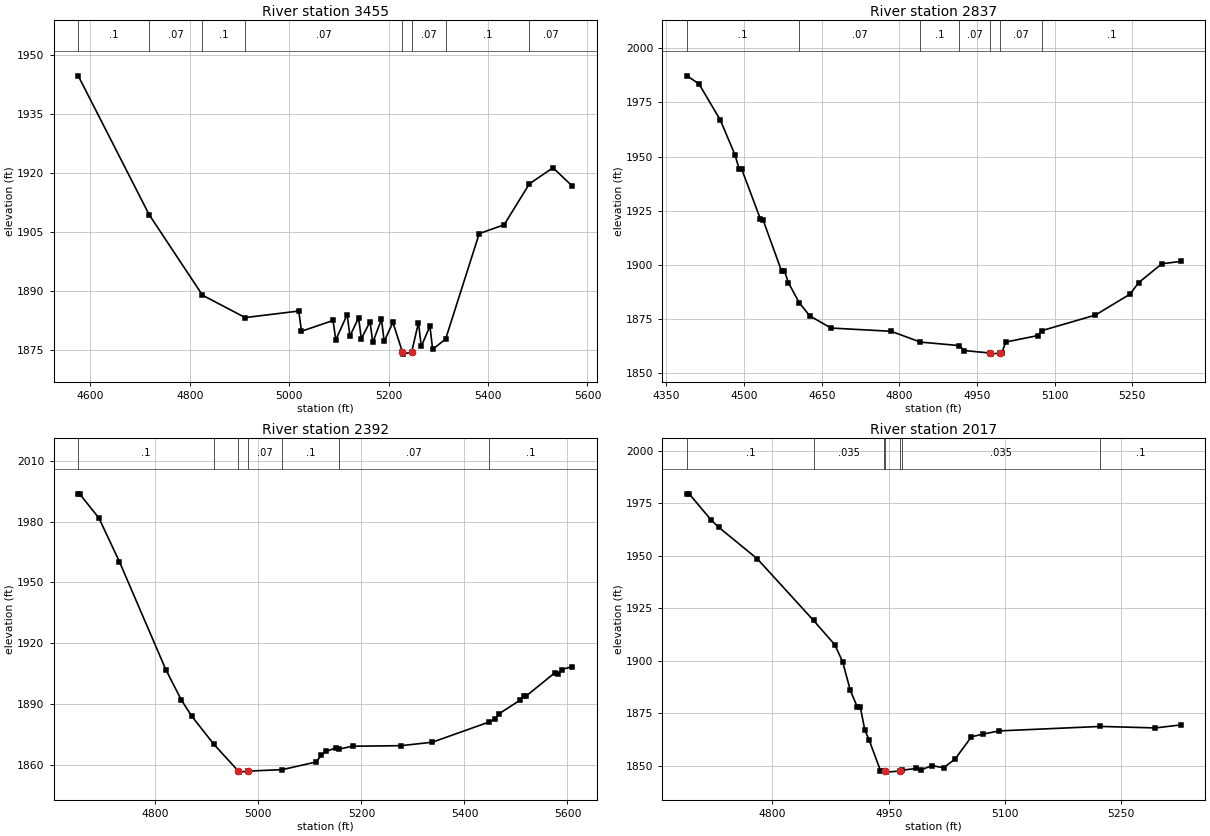
Type RM Length L Ch R = 1 ,3455    ,618,618,618
BEGIN DESCRIPTION:
Fessenden Branch 7.1
END DESCRIPTION:
XS GIS Cut Line= 4
      1859944.89     13970141.32      1859738.69     13970273.72
      1859261.26     13970054.54      1859038.92     13970037.27
#Sta/Elev= 30
  4575.4 1944.71  4718.1 1909.42  4825.4 1888.95  4911.3 1883.26  5019.1 1884.92
  5024.6 1879.79  5088.1 1882.52  5093.6 1877.58  5116.5 1884.03    5122 1878.56
  5139.5 1883.18    5145 1877.86  5162.5 1882.21    5168 1876.93  5185.5 1882.82
    5191 1877.19  5208.5 1882.03  5227.8 1874.47  5228.3 1873.97  5246.2 1874.47
    5260 1881.99  5265.5 1875.93    5283 1881.08  5288.5 1875.19  5314.6  1877.8
  5382.2 1904.61  5432.3 1906.84  5483.1 1917.26  5530.6 1921.34  5568.8 1916.77
#Mann= 8 ,-1 , 0
  4575.4      .1       0  4718.1     .07       0  4825.4      .1       0
  4911.3     .07       0  5227.8     .05       0  5246.2     .07       0
  5314.6      .1       0  5483.1     .07       0
Bank Sta=5227.8,5246.2
XS Rating Curve= 0 ,0
Exp/Cntr=0.3,0.1

Type RM Length L Ch R = 1 ,2837    ,445,445,445
BEGIN DESCRIPTION:
Fessenden Branch 6.0
END DESCRIPTION:
XS GIS Cut Line= 3
        1860075.       13969625.        1859475.       13969775.
      1859174.97     13969925.01
#Sta/Elev= 30
  4389.6 1987.31  4412.8 1983.57    4454 1966.88  4482.4 1950.76  4490.1 1944.49
  4495.2 1944.26  4531.3 1921.26  4536.5  1920.8  4572.6 1896.95  4577.7 1897.34
  4585.4 1891.83  4606.2 1882.58  4626.7 1876.44  4667.9  1870.8  4783.9  1869.3
  4840.7  1864.3  4915.2 1862.71  4925.6 1860.39  4975.7 1859.25  4976.2 1858.75
  4994.1 1859.25  4997.8 1859.34  5005.5 1864.34  5066.8 1867.29  5075.8 1869.65
  5178.6 1876.78  5245.6 1886.48  5262.4 1891.81  5307.1  1900.5  5343.5 1901.56
#Mann= 7 ,-1 , 0
  4389.6      .1       0  4606.2     .07       0  4840.7      .1       0
  4915.2     .07       0  4975.7     .05       0  4994.1     .07       0
  5075.8      .1       0
Bank Sta=4975.7,4994.1
XS Rating Curve= 0 ,0
Exp/Cntr=0.3,0.1

Type RM Length L Ch R = 1 ,2392    ,375,375,375
BEGIN DESCRIPTION:
Fessenden Branch 5.0
END DESCRIPTION:
XS GIS Cut Line= 3
      1860075.05       13969425.        1859725.       13969425.
      1859125.02       13969525.
#Sta/Elev= 30
  4650.4 1993.64  4652.9 1993.64  4690.4 1981.79  4730.4  1960.2  4820.4  1907.1
  4850.4  1892.2  4870.4 1884.28  4913.5 1870.38  4961.2 1857.12  4961.7 1856.62
  4979.6 1857.12  5046.5 1857.85    5112 1861.61  5122.1 1864.87  5132.2 1866.88
    5150 1868.54  5155.8 1867.93  5182.9 1869.37  5276.7 1869.64  5337.5 1871.34
  5448.6 1881.36  5459.2 1882.78  5466.8  1885.3  5507.3 1891.94  5514.9 1894.19
    5520 1894.12  5575.8  1905.6  5580.8 1904.78  5588.4 1907.11  5608.7 1908.52
#Mann= 7 ,-1 , 0
  4650.4      .1       0  4913.5     .07       0  4961.2     .05       0
  4979.6     .07       0  5046.5      .1       0  5155.8     .07       0
  5448.6      .1       0
Bank Sta=4961.2,4979.6
XS Rating Curve= 0 ,0
Exp/Cntr=0.3,0.1

Type RM Length L Ch R = 1 ,2017    ,91,91,91
BEGIN DESCRIPTION:
Fessenden Branch 4.1
END DESCRIPTION:
XS GIS Cut Line= 5
      1859955.67     13969006.36      1859732.18     13969006.36
      1859706.14     13969017.21      1859673.59      13969069.3
      1859404.52      13969249.4
#Sta/Elev= 30
  4689.8 1979.41  4692.6 1979.41  4720.5 1967.14  4730.5 1963.55  4780.5 1948.46
  4853.1 1919.09  4880.5 1907.54  4890.5 1899.49  4900.5 1885.81  4909.4 1877.95
  4913.3 1877.95  4919.2 1866.97  4924.6 1862.31  4939.4 1847.61  4943.5  1847.5
  4945.6 1847.38  4946.1 1846.88  4964.1 1847.38  4966.9 1847.78  4985.5 1848.63
  4991.4 1847.84  5005.7 1850.03  5020.7 1848.94  5035.7 1853.14  5056.7 1863.68
  5071.8 1865.02  5092.8 1866.52  5223.2 1868.64  5293.9 1867.93  5326.7 1869.35
#Mann= 7 ,-1 , 0
  4689.8      .1       0  4853.1    .035       0  4943.5     .07       0
  4945.6     .05       0  4964.1     .07       0  4966.9    .035       0
  5223.2      .1       0
Bank Sta=4945.6,4964.1
XS Rating Curve= 0 ,0
Exp/Cntr=0.3,0.1