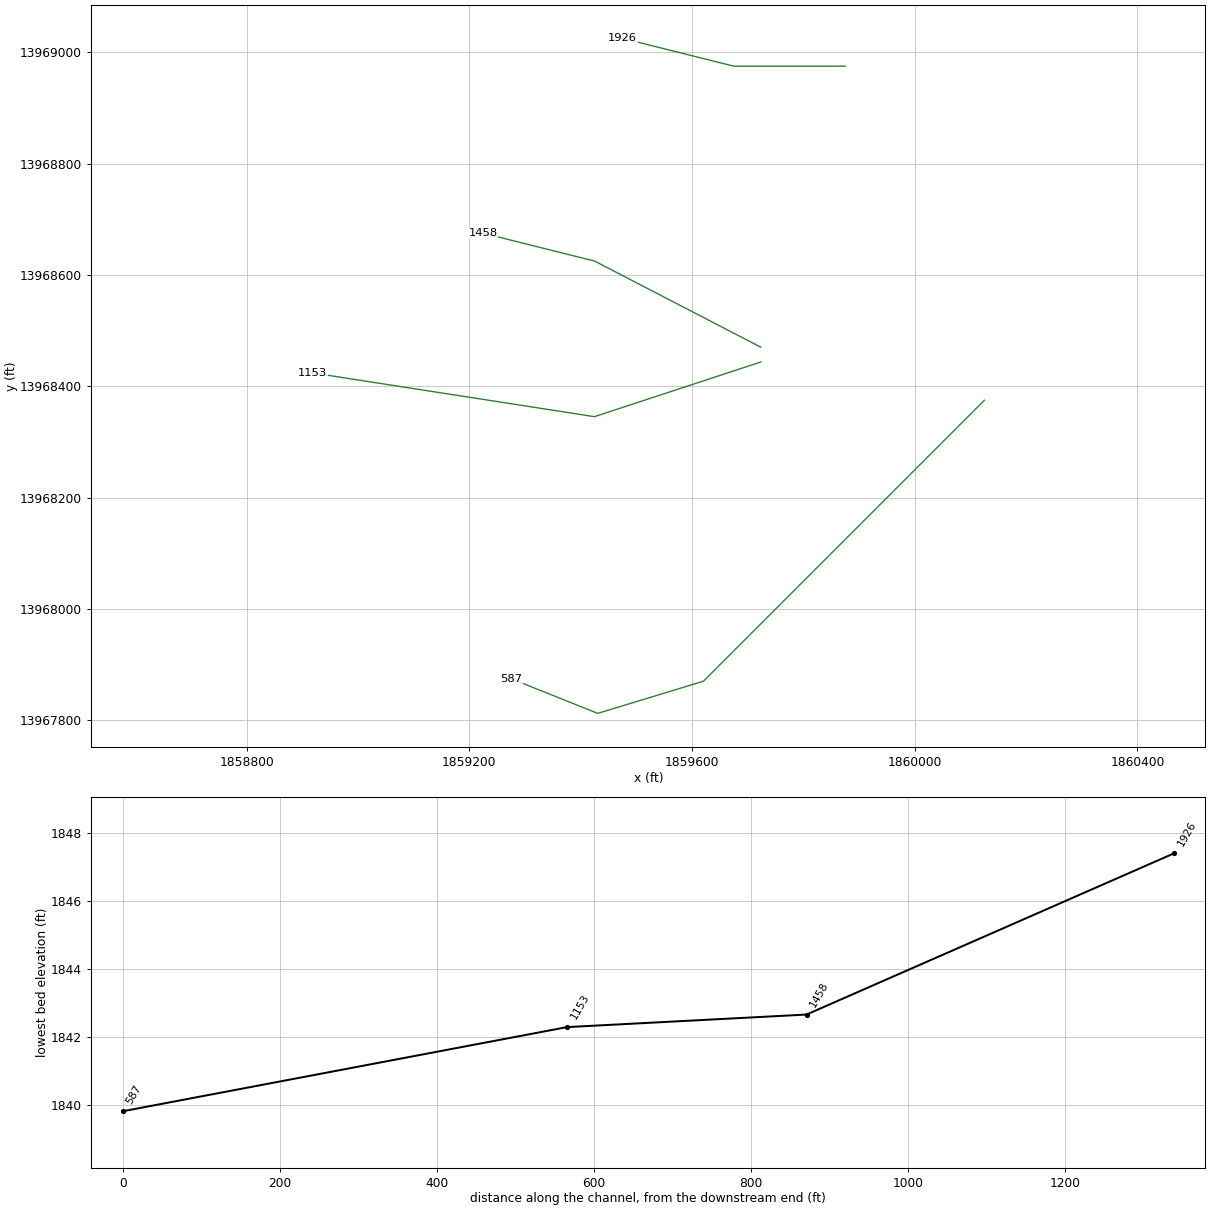
HEC-RAS study Fessenden Branch.prj: Fessenden Branch Base Level Engineering

--- Fessenden Branch.g01 (geometry) --- (continued)

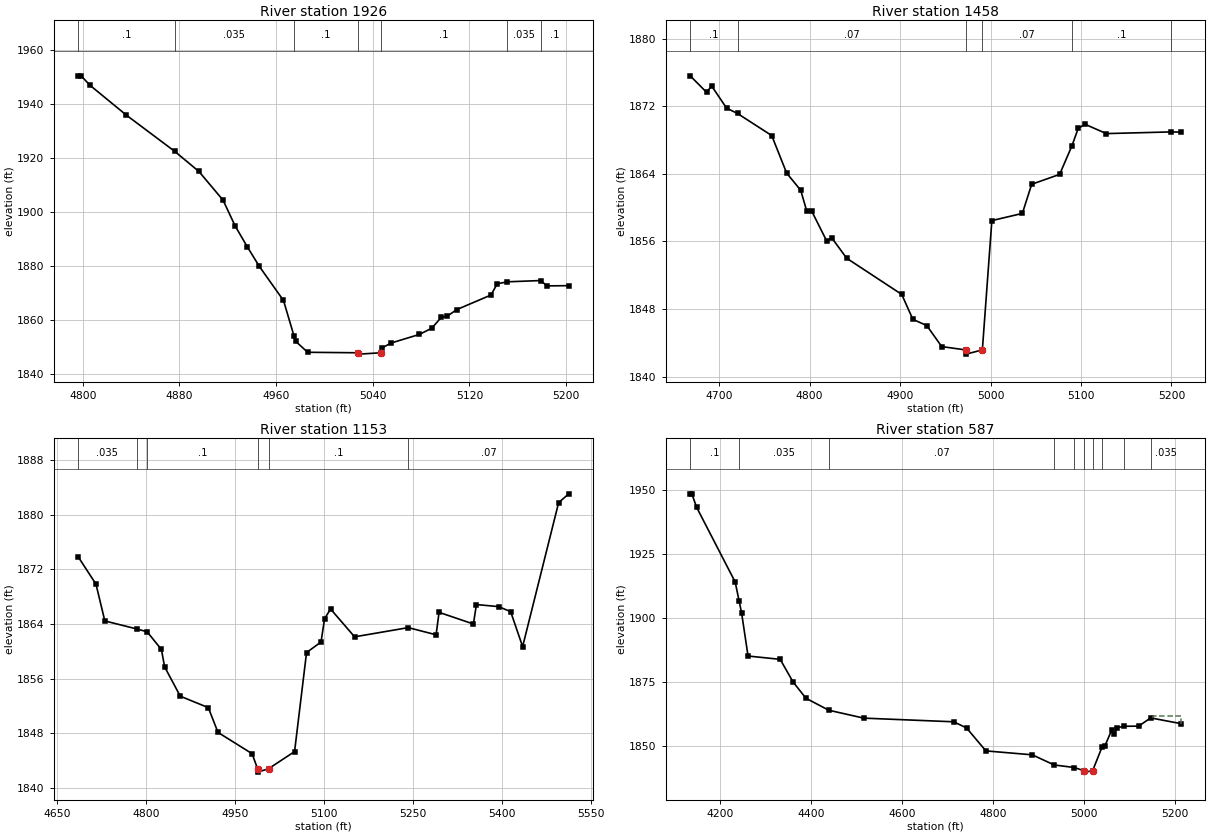
Type RM Length L Ch R = 1 ,1926    ,468,468,468
BEGIN DESCRIPTION:
Fessenden Branch 4.0
END DESCRIPTION:
XS GIS Cut Line= 3
      1859874.98       13968975.        1859675.       13968975.
      1859475.03     13969024.99
#Sta/Elev= 30
  4796.1  1950.4  4798.6  1950.4  4806.1 1946.85  4836.1 1935.84  4876.1 1922.44
  4896.1 1915.01  4916.1 1904.37  4926.1 1894.83  4936.1 1887.16  4946.1 1879.88
  4966.1 1867.26  4974.7  1854.3  4976.1 1852.19  4986.1 1848.09  5028.1 1847.91
  5028.6 1847.41  5046.6 1847.91  5047.6 1849.71  5055.3 1851.54  5078.5 1854.69
  5088.8    1857  5096.6 1860.97  5101.7 1861.48  5109.5 1863.89  5137.8 1869.28
    5143 1873.44  5151.4 1874.17  5178.9 1874.64  5184.2 1872.66  5202.2 1872.75
#Mann= 7 ,-1 , 0
  4796.1      .1       0  4876.1    .035       0  4974.7      .1       0
  5028.1     .05       0  5046.6      .1       0  5151.4    .035       0
  5178.9      .1       0
Bank Sta=5028.1,5046.6
XS Rating Curve= 0 ,0
Exp/Cntr=0.3,0.1

Type RM Length L Ch R = 1 ,1458    ,305,305,305
BEGIN DESCRIPTION:
Fessenden Branch 3.0
END DESCRIPTION:
XS GIS Cut Line= 3
      1859723.49     13968470.34        1859425.       13968625.
      1859225.03     13968674.99
#Sta/Elev= 30
  4668.1 1875.61  4686.2 1873.66  4691.8 1874.41  4708.3 1871.79  4720.4 1871.15
  4758.2 1868.54  4774.7  1864.1  4790.3 1862.05  4796.8 1859.64  4802.5 1859.57
    4819 1856.05  4824.6 1856.42  4841.1 1854.01  4901.9 1849.73  4914.2 1846.78
  4929.6 1846.04  4946.1 1843.55  4972.5 1843.16    4973 1842.66    4991 1843.16
  5001.5 1858.47  5035.2 1859.32  5045.5 1862.77  5076.4 1863.94  5090.1 1867.35
    5097 1869.41  5104.8 1869.86    5128 1868.77  5199.6 1868.97  5210.4 1868.94
#Mann= 6 ,-1 , 0
  4668.1      .1       0  4720.4     .07       0  4972.5     .05       0
    4991     .07       0  5090.1      .1       0  5199.6     .07       0
Bank Sta=4972.5,4991
XS Rating Curve= 0 ,0
Exp/Cntr=0.3,0.1

Type RM Length L Ch R = 1 ,1153    ,566,566,566
BEGIN DESCRIPTION:
Fessenden Branch 2.0
END DESCRIPTION:
XS GIS Cut Line= 3
      1859723.65     13968443.79      1859424.77     13968345.56
      1858918.14     13968424.18
#Sta/Elev= 30
  4685.5 1873.87  4715.7 1869.84  4730.6 1864.45  4784.2 1863.28  4801.9 1862.86
    4826 1860.27  4831.4 1857.72  4857.8 1853.42  4905.1 1851.74  4921.4 1848.11
  4978.8    1845  4988.1 1842.79  4988.6 1842.29  5006.6 1842.79  5050.5  1845.3
  5070.7 1859.82  5095.1 1861.36  5101.1 1864.78  5111.2  1866.2  5151.7 1862.12
  5242.2 1863.47  5289.1 1862.42  5294.1 1865.71    5352    1864  5357.1 1866.85
  5394.5 1866.55  5414.8 1865.81    5435 1860.69  5495.7 1881.79  5512.8 1883.08
#Mann= 6 ,-1 , 0
  4685.5    .035       0  4784.2     .07       0  4801.9      .1       0
  4988.1     .05       0  5006.6      .1       0  5242.2     .07       0
#XS Ineff= 2 , 0
                         5112.92         1864.68
Permanent Ineff=
       F       F
#Block Obstruct= 2 , 0
                         5110.34         1863.61
Bank Sta=4988.1,5006.6
XS Rating Curve= 0 ,0
Exp/Cntr=0.3,0.1

Type RM Length L Ch R = 1 ,587     ,0,0,0
BEGIN DESCRIPTION:
Fessenden Branch 1.0
END DESCRIPTION:
XS GIS Cut Line= 4
      1860125.02     13968375.02      1859620.49     13967870.49
      1859430.73     13967812.71        1859275.       13967875.
#Sta/Elev= 30
  4133.4 1948.35    4137 1948.35  4147.6 1943.08  4232.4 1913.96  4241.1 1906.52
  4246.6 1901.82  4260.7 1885.09  4331.4  1883.8  4359.7 1874.99    4388 1868.64
  4438.1 1863.96  4515.3 1860.87  4713.3 1859.44  4741.5 1857.03    4784 1848.09
  4886.1 1846.56  4934.2 1842.61  4978.6 1841.61  5000.2 1840.31  5000.7 1839.81
  5018.7 1840.31  5039.2 1849.42  5045.3 1849.82  5060.9 1856.26  5066.3 1854.61
    5073 1857.16  5088.5  1857.7  5120.1 1857.74  5146.5 1860.96    5213 1858.73
#Mann= 10 ,-1 , 0
  4133.4      .1       0  4241.1    .035       0  4438.1     .07       0
  4934.2      .1       0  4978.6     .07       0  5000.2     .05       0
  5018.7     .07       0  5039.2    .035       0  5088.5     .07       0
  5146.5    .035       0
#XS Ineff= 2 , 0
                          5152.2         1861.59
Permanent Ineff=
       F       F
#Block Obstruct= 2 , 0
                         5150.39         1861.63
Bank Sta=5000.2,5018.7
XS Rating Curve= 0 ,0
Exp/Cntr=0.3,0.1

Chan Stop Cuts=-1
Use User Specified Reach Order=0
Composite Channel Slope=5