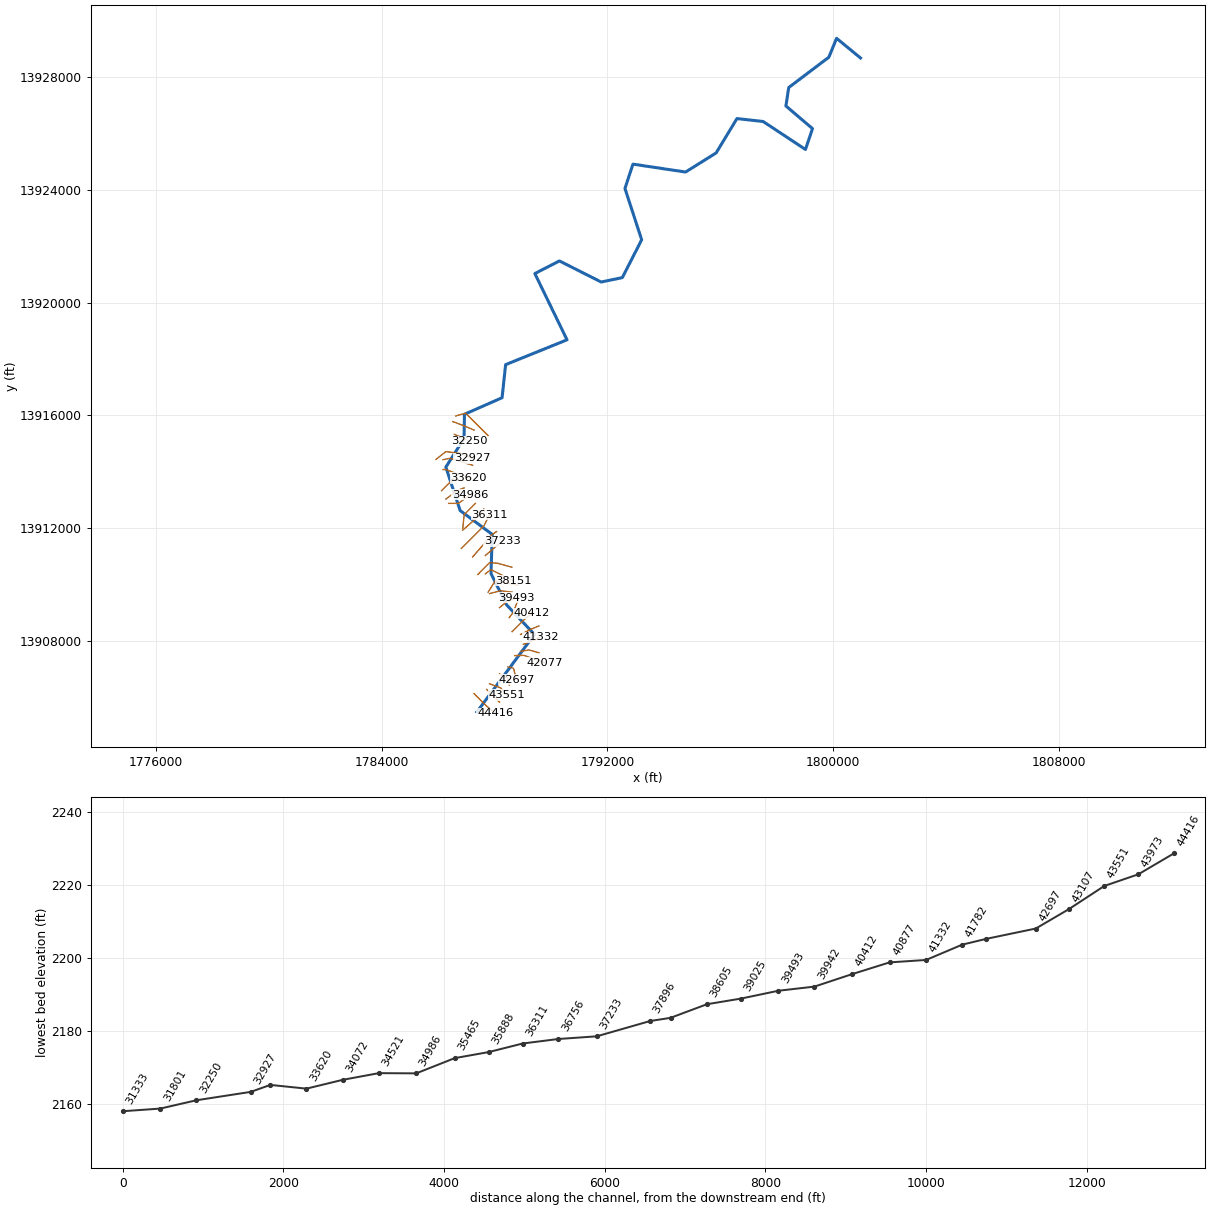
--- Flat Rock Creek 2.prj (project) ---

Proj Title=Flat Rock Creek 2 Base Level Engineering
Current Plan=p01
Default Exp/Contr=0.3,0.1
English Units
Geom File=g01
Flow File=f01
Plan File=p01
BEGIN DESCRIPTION:
Flat Rock Creek 2
END DESCRIPTION:

--- Flat Rock Creek 2.p01 (plan) ---

Plan Title=Multiple Run
Short Identifier=Multiple
Geom File=g01
Flow File=f01
Subcritical Flow
K Sum by GR= 0
Std Step Tol= 0.01
Critical Tol= 0.01
Num of Std Step Trials= 20
Max Error Tol= 0.3
Flow Tol Ratio= 0.001
Split Flow NTrial= 30
Split Flow Tol= 0.02
Split Flow Ratio= 0.02
Log Output Level= 0
Friction Slope Method= 1
Unsteady Friction Slope Method= 2
Unsteady Bridges Friction Slope Method= 1
Parabolic Critical Depth
Global Vel Dist=  1 , 1 , 1
Global Log Level= 0
CheckData=True
Encroach Param= -1, 0, 0, 0
BEGIN DESCRIPTION:
Multiple Run
END DESCRIPTION:

--- Flat Rock Creek 2.f01 (steady flow) ---

Flow Title=Multiple
Number of Profiles=7
Profile Names=10-year,25-year,50-year,1pct_min,100-year,1pct_plu,500-year
River Rch & RM= Flat Rock Creek ,Reach-1,44416
    1249    2138    2984    2010    4010    8000    7162
River Rch & RM= Flat Rock Creek ,Reach-1,42077
    2265    4005    5709    3918    7817   15597   14520
River Rch & RM= Flat Rock Creek ,Reach-1,35888
    2641    4692    6712    4619    9216   18389   17214
River Rch & RM= Flat Rock Creek ,Reach-1,32250
    2902    5163    7391    5086   10149   20249   18951
River Rch & RM= Flat Rock Creek ,Reach-1,27172
    3220    5756    8267    5706   11385   22715   21387
River Rch & RM= Flat Rock Creek ,Reach-1,23754
    3522    6309    9072    6266   12503   24947   23526
River Rch & RM= Flat Rock Creek ,Reach-1,17709
    3829    6878    9908    6856   13679   27293   25825
River Rch & RM= Flat Rock Creek ,Reach-1,14518
    3928    7061   10177    7045   14056   28045   26557
River Rch & RM= Flat Rock Creek ,Reach-1,13112
    3985    7165   10327    7148   14262   28457   26946
River Rch & RM= Flat Rock Creek ,Reach-1,10908
    4055    7292   10511    7276   14517   28966   27430
River Rch & RM= Flat Rock Creek ,Reach-1,7721
    4363    7869   11366    7882   15726   31377   29821
Boundary for River Rch & Prof#=Flat Rock Creek ,Reach-1,1
Up Type=0
Dn Type=3
Dn Slope=0.005
Boundary for River Rch & Prof#=Flat Rock Creek ,Reach-1,2
Up Type=0
Dn Type=3
Dn Slope=0.005
Boundary for River Rch & Prof#=Flat Rock Creek ,Reach-1,3
Up Type=0
Dn Type=3
Dn Slope=0.005
Boundary for River Rch & Prof#=Flat Rock Creek ,Reach-1,4
Up Type=0
Dn Type=3
Dn Slope=0.005
Boundary for River Rch & Prof#=Flat Rock Creek ,Reach-1,5
Up Type=0
Dn Type=3
Dn Slope=0.005
Boundary for River Rch & Prof#=Flat Rock Creek ,Reach-1,6
Up Type=0
Dn Type=3
Dn Slope=0.005
Boundary for River Rch & Prof#=Flat Rock Creek ,Reach-1,7
Up Type=0
Dn Type=3
Dn Slope=0.005

--- Flat Rock Creek 2.g01 (geometry) ---

Geom Title=Existing Conditions

River Reach=Flat Rock Creek ,Reach-1
Reach XY= 30
      1787375.00     13905475.00      1789417.24     13908224.92
      1788430.52     13909272.57      1787876.05     13910385.44
      1787921.39     13911773.50      1786782.76     13912618.79
      1786275.51     13914159.79      1786921.25     13915176.55
      1786935.48     13916034.80      1788269.16     13916622.71
      1788394.52     13917795.50      1790571.26     13918676.56
      1789430.83     13921027.30      1790302.31     13921475.09
      1791780.93     13920727.23      1792531.19     13920882.82
      1793217.47     13922224.99      1792625.26     13924045.28
      1792908.07     13924908.59      1794773.45     13924628.75
      1795855.50     13925304.53      1796594.98     13926525.04
      1797523.50     13926421.38      1799023.52     13925428.61
      1799272.93     13926169.14      1798330.36     13926972.30
      1798430.83     13927627.30      1799852.12     13928701.37
      1800126.46     13929371.48      1800975.00     13928675.00

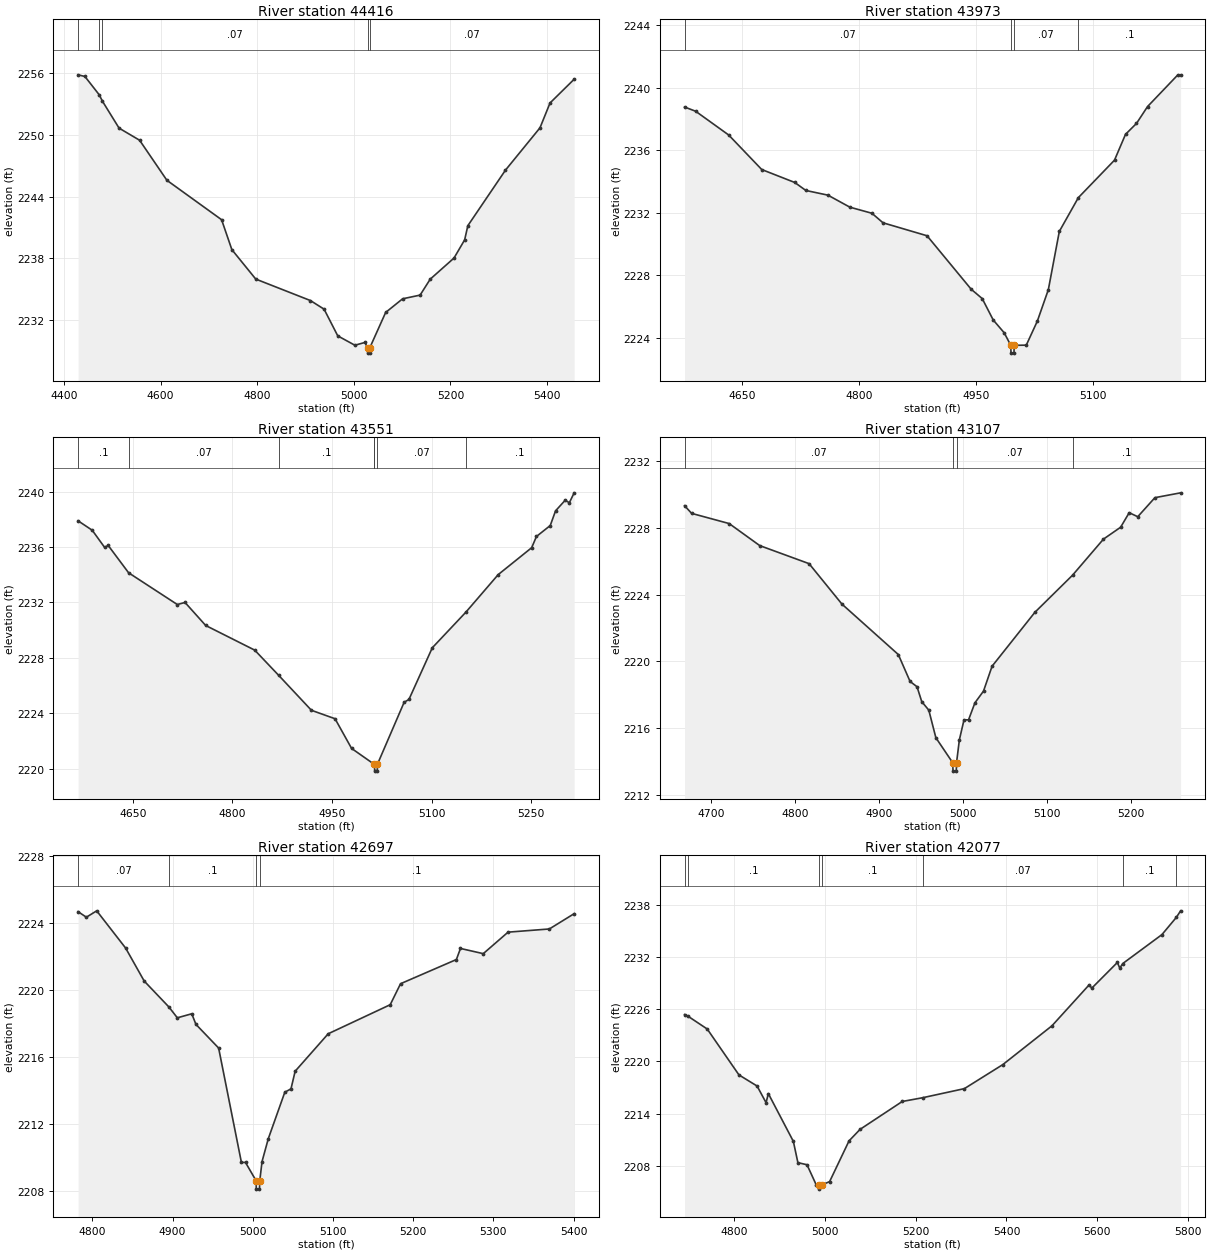
Type RM Length L Ch R = 1,44416,443,443,443
BEGIN DESCRIPTION:
Stream0146 35.0
END DESCRIPTION:
XS GIS Cut Line= 3
      1787275.01     13906124.99      1787675.00     13905725.00
      1788024.97     13905425.03
#Sta/Elev= 30
  4429.3 2255.85  4443.4 2255.69  4473.1 2253.90  4479.7 2253.28  4514.1 2250.66
  4556.6 2249.48  4613.1 2245.58  4726.3 2241.74  4747.5 2238.83  4797.0 2235.96
  4910.1 2233.87  4938.4 2233.03  4966.7 2230.43  5002.1 2229.52  5023.0 2229.79
  5028.4 2229.25  5028.7 2228.75  5032.5 2228.75  5032.8 2229.25  5065.8 2232.71
  5100.9 2234.04  5137.1 2234.40  5158.0 2235.95  5207.3 2238.01  5229.3 2239.78
  5235.9 2241.16  5313.8 2246.57  5385.2 2250.69  5406.0 2253.11  5455.9 2255.42
#Mann=5,-1,0
  4429.3    0.07       0  4473.1     0.1       0  4479.7    0.07       0
  5028.4    0.05       0  5032.8    0.07       0
Bank Sta=5028.4,5032.8
Exp/Cntr=0.3,0.1

Type RM Length L Ch R = 1,43973,422,422,422
BEGIN DESCRIPTION:
Stream0146 34.0
END DESCRIPTION:
XS GIS Cut Line= 3
      1787724.99     13906275.01      1788025.00     13905975.00
      1788174.99     13905825.01
#Sta/Elev= 30
  4575.7 2238.76  4589.9 2238.49  4632.3 2236.97  4674.7 2234.76  4717.1 2233.93
  4731.3 2233.42  4759.6 2233.12  4787.8 2232.35  4816.1 2231.96  4830.3 2231.35
  4886.8 2230.52  4943.4 2227.10  4957.6 2226.50  4971.7 2225.13  4985.8 2224.31
  4994.2 2223.51  4994.5 2223.01  4998.3 2223.01  4998.6 2223.51  5014.1 2223.52
  5028.3 2225.06  5042.4 2227.07  5056.5 2230.80  5080.9 2232.96  5127.3 2235.36
  5141.4 2237.01  5155.5 2237.71  5169.7 2238.79  5208.6 2240.82  5212.1 2240.82
#Mann=4,-1,0
  4575.7    0.07       0  4994.2    0.05       0  4998.6    0.07       0
  5080.9     0.1       0
Bank Sta=4994.2,4998.6
Exp/Cntr=0.3,0.1

Type RM Length L Ch R = 1,43551,444,444,444
BEGIN DESCRIPTION:
Stream0146 33.0
END DESCRIPTION:
XS GIS Cut Line= 3
      1787825.03     13906474.99      1788225.00     13906325.00
      1788424.99     13906075.02
#Sta/Elev= 30
  4567.5 2237.89  4588.8 2237.21  4607.5 2235.97  4612.9 2236.11  4643.6 2234.14
  4717.0 2231.85  4728.6 2232.00  4759.7 2230.34  4833.6 2228.56  4869.7 2226.74
  4919.0 2224.22  4954.6 2223.61  4979.5 2221.47  5013.4 2220.33  5014.0 2220.33
  5014.3 2219.83  5018.2 2219.83  5018.5 2220.33  5058.7 2224.80  5065.9 2225.00
  5101.1 2228.73  5151.7 2231.30  5200.4 2234.01  5250.8 2235.95  5258.0 2236.76
  5278.8 2237.55  5286.8 2238.61  5301.2 2239.37  5307.6 2239.20  5314.8 2239.91
#Mann=7,-1,0
  4567.5     0.1       0  4643.6    0.07       0  4869.7     0.1       0
  5013.4    0.07       0  5014.0    0.05       0  5018.5    0.07       0
  5151.7     0.1       0
Bank Sta=5014,5018.5
Exp/Cntr=0.3,0.1

Type RM Length L Ch R = 1,43107,410,410,410
BEGIN DESCRIPTION:
Stream0146 32.0
END DESCRIPTION:
XS GIS Cut Line= 3
      1788174.98     13906825.01      1788475.00     13906675.00
      1788525.00     13906424.99
#Sta/Elev= 30
  4668.9 2229.32  4677.3 2228.86  4722.0 2228.25  4758.4 2226.93  4817.1 2225.85
  4856.2 2223.43  4923.3 2220.41  4937.3 2218.80  4945.6 2218.48  4951.2 2217.59
  4959.6 2217.08  4968.0 2215.43  4988.1 2213.93  4988.4 2213.43  4992.3 2213.43
  4992.6 2213.93  4996.0 2215.31  5001.5 2216.50  5006.9 2216.50  5014.5 2217.52
  5024.7 2218.22  5034.9 2219.71  5085.9 2222.94  5130.7 2225.16  5167.5 2227.32
  5187.9 2228.03  5198.1 2228.90  5208.3 2228.66  5228.7 2229.80  5259.3 2230.09
#Mann=4,-1,0
  4668.9    0.07       0  4988.1    0.05       0  4992.6    0.07       0
  5130.7     0.1       0
Bank Sta=4988.1,4992.6
Exp/Cntr=0.3,0.1

Type RM Length L Ch R = 1,42697,620,620,620
BEGIN DESCRIPTION:
Stream0146 31.0
END DESCRIPTION:
XS GIS Cut Line= 3
      1788475.02     13907075.00      1788675.00     13907025.00
      1788774.99     13906625.05
#Sta/Elev= 30
  4782.3 2224.66  4792.6 2224.33  4805.5 2224.71  4841.6 2222.49  4864.7 2220.53
  4895.6 2218.98  4906.0 2218.34  4924.0 2218.58  4929.2 2217.95  4957.5 2216.54
  4985.9 2209.73  4991.0 2209.73  5004.2 2208.64  5004.5 2208.14  5008.4 2208.14
  5008.8 2208.64  5011.6 2209.78  5019.4 2211.14  5040.0 2213.91  5047.7 2214.11
  5052.9 2215.16  5094.1 2217.39  5171.4 2219.12  5184.3 2220.37  5253.9 2221.81
  5259.0 2222.47  5287.4 2222.16  5318.3 2223.44  5369.8 2223.63  5400.7 2224.54
#Mann=4,-1,0
  4782.3    0.07       0  4895.6     0.1       0  5004.2    0.05       0
  5008.8     0.1       0
Bank Sta=5004.2,5008.8
Exp/Cntr=0.3,0.1

Type RM Length L Ch R = 1,42077,295,295,295
BEGIN DESCRIPTION:
Stream0146 30.0
END DESCRIPTION:
XS GIS Cut Line= 3
      1788725.05     13907475.00      1789039.13     13907483.51
      1789775.04     13907224.99
#Sta/Elev= 30
  4689.9 2225.41  4696.5 2225.25  4739.9 2223.74  4809.9 2218.45  4849.9 2217.17
  4869.7 2215.25  4874.7 2216.30  4929.9 2210.79  4939.9 2208.34  4960.0 2208.10
  4980.0 2205.82  4986.5 2205.79  4987.0 2205.29  4993.5 2205.79  5009.9 2206.16
  5052.7 2210.85  5077.1 2212.18  5170.1 2215.39  5214.8 2215.82  5307.1 2216.87
  5391.9 2219.64  5500.3 2224.11  5582.7 2228.85  5588.0 2228.44  5644.6 2231.41
  5649.9 2230.76  5656.6 2231.29  5742.9 2234.62  5774.6 2236.60  5784.1 2237.36
#Mann=7,-1,0
  4689.9    0.07       0  4696.5     0.1       0  4986.5    0.05       0
  4993.5     0.1       0  5214.8    0.07       0  5656.6     0.1       0
  5774.6    0.07       0
Bank Sta=4986.5,4993.5
Exp/Cntr=0.3,0.1

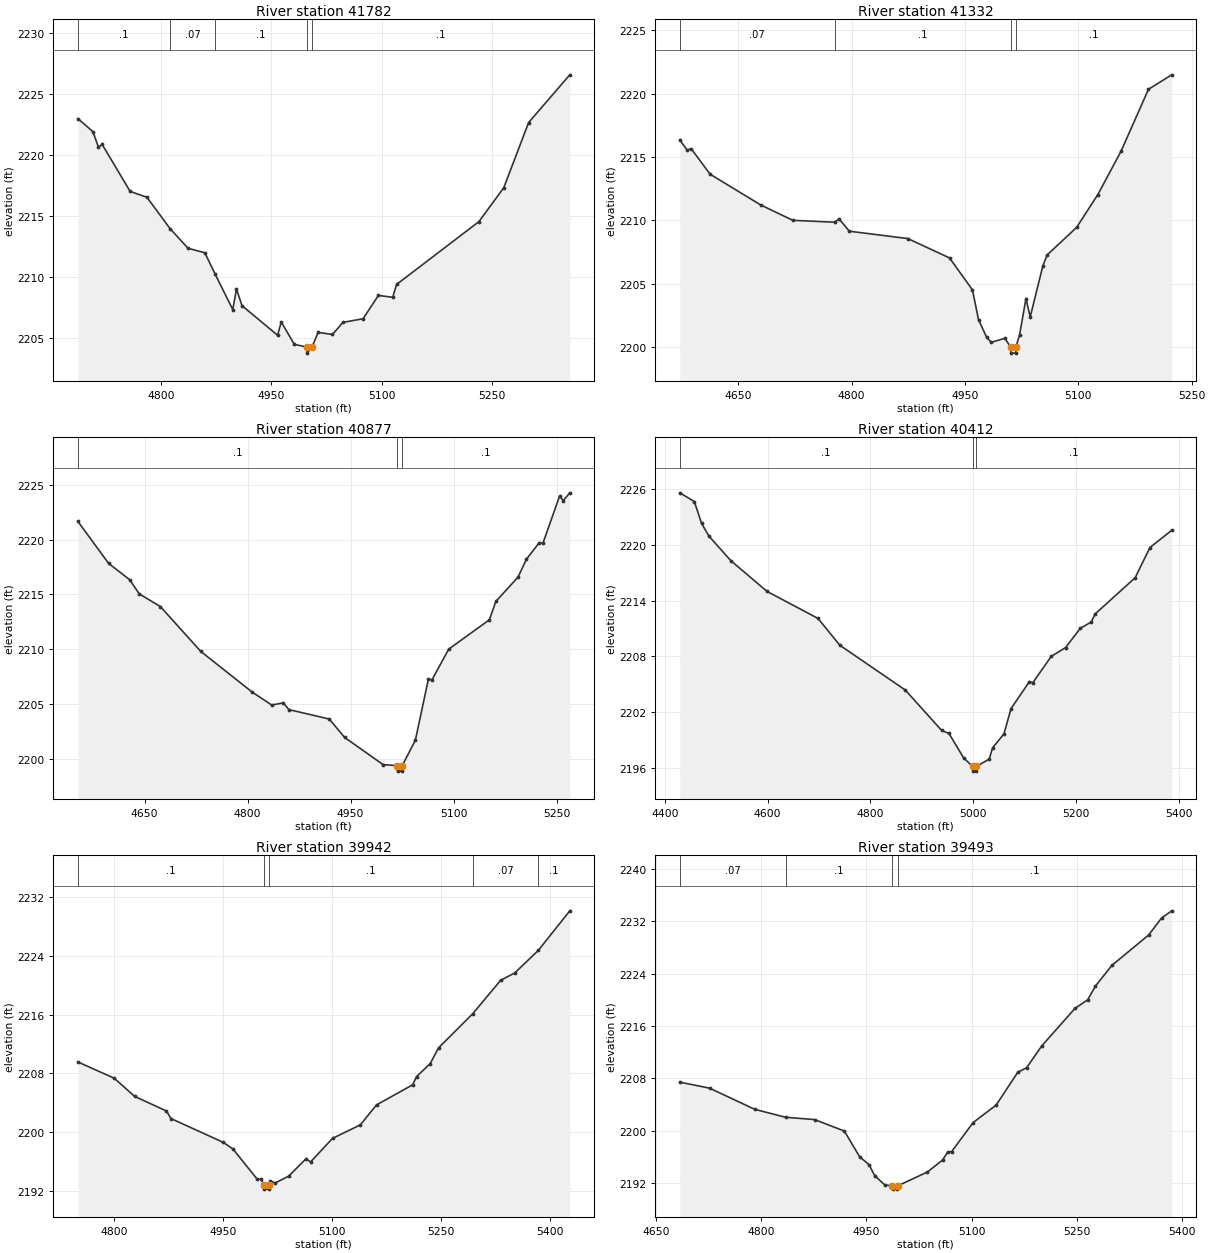
Type RM Length L Ch R = 1,41782,450,450,450
BEGIN DESCRIPTION:
Stream0146 29.0
END DESCRIPTION:
XS GIS Cut Line= 3
      1788924.99     13907625.00      1789225.00     13907675.00
      1789575.04     13907574.99
#Sta/Elev= 30
  4687.5 2222.95  4707.8 2221.89  4715.4 2220.62  4720.5 2220.83  4758.5 2216.98
  4781.3 2216.50  4812.7 2213.93  4837.1 2212.32  4859.9 2211.95  4874.1 2210.18
  4897.9 2207.29  4902.9 2208.97  4910.5 2207.61  4958.7 2205.19  4963.8 2206.27
  4981.5 2204.44  4998.5 2204.22  4999.0 2203.72  5005.6 2204.22  5013.8 2205.42
  5033.3 2205.25  5047.6 2206.24  5074.9 2206.54  5095.7 2208.45  5115.2 2208.30
  5120.4 2209.35  5232.2 2214.50  5266.0 2217.28  5299.8 2222.63  5355.7 2226.54
#Mann=5,-1,0
  4687.5     0.1       0  4812.7    0.07       0  4874.1     0.1       0
  4998.5    0.05       0  5005.6     0.1       0
Bank Sta=4998.5,5005.6
Exp/Cntr=0.3,0.1

Type RM Length L Ch R = 1,41332,455,455,455
BEGIN DESCRIPTION:
Stream0146 28.0
END DESCRIPTION:
XS GIS Cut Line= 3
      1789024.98     13907874.99      1789425.00     13908025.00
      1789624.98     13908124.99
#Sta/Elev= 30
  4572.7 2216.34  4582.5 2215.54  4587.8 2215.65  4612.8 2213.64  4679.5 2211.22
  4722.2 2210.00  4777.4 2209.85  4783.6 2210.10  4797.0 2209.14  4874.4 2208.56
  4929.6 2207.03  4959.9 2204.51  4967.9 2202.17  4978.6 2200.78  4984.8 2200.37
  5002.7 2200.69  5010.3 2200.02  5010.8 2199.52  5017.0 2199.52  5017.5 2200.02
  5022.3 2200.98  5030.7 2203.83  5036.3 2202.37  5053.0 2206.39  5058.6 2207.26
  5097.7 2209.44  5125.7 2212.02  5156.4 2215.44  5192.8 2220.34  5223.5 2221.48
#Mann=4,-1,0
  4572.7    0.07       0  4777.4     0.1       0  5010.3    0.05       0
  5017.5     0.1       0
Bank Sta=5010.3,5017.5
Exp/Cntr=0.3,0.1

Type RM Length L Ch R = 1,40877,465,465,465
BEGIN DESCRIPTION:
Stream0146 27.0
END DESCRIPTION:
XS GIS Cut Line= 3
      1788925.01     13908225.01      1789325.00     13908425.00
      1789575.04     13908525.02
#Sta/Elev= 30
  4552.8 2221.66  4597.5 2217.83  4628.3 2216.33  4642.2 2215.04  4673.0 2213.88
  4731.7 2209.79  4807.1 2206.05  4835.1 2204.89  4851.9 2205.08  4860.2 2204.47
  4918.9 2203.61  4941.3 2201.93  4997.2 2199.45  5017.9 2199.35  5018.4 2198.85
  5024.7 2198.85  5025.2 2199.35  5044.4 2201.68  5063.3 2207.24  5068.7 2207.20
  5092.9 2209.99  5152.1 2212.67  5161.6 2214.35  5193.9 2216.57  5206.0 2218.19
  5224.8 2219.72  5230.2 2219.67  5254.4 2223.97  5259.8 2223.56  5269.3 2224.27
#Mann=3,-1,0
  4552.8     0.1       0  5017.9    0.05       0  5025.2     0.1       0
Bank Sta=5017.9,5025.2
Exp/Cntr=0.3,0.1

Type RM Length L Ch R = 1,40412,470,470,470
BEGIN DESCRIPTION:
Stream0146 26.0
END DESCRIPTION:
XS GIS Cut Line= 3
      1788625.01     13908325.01      1789025.00     13908725.00
      1789325.01     13908975.01
#Sta/Elev= 30
  4429.3 2225.64  4457.6 2224.70  4471.7 2222.34  4485.9 2220.98  4528.3 2218.34
  4599.0 2215.01  4698.0 2212.10  4740.4 2209.21  4867.7 2204.38  4938.4 2200.02
  4952.6 2199.70  4980.8 2197.09  4998.4 2196.14  4998.9 2195.64  5005.4 2195.64
  5005.9 2196.14  5030.8 2196.94  5037.3 2198.15  5059.4 2199.65  5073.1 2202.37
  5108.9 2205.29  5115.4 2205.16  5151.2 2208.00  5179.2 2208.96  5207.8 2211.03
  5229.3 2211.72  5236.4 2212.57  5314.5 2216.49  5343.2 2219.74  5385.5 2221.60
#Mann=3,-1,0
  4429.3     0.1       0  4998.4    0.05       0  5005.9     0.1       0
Bank Sta=4998.4,5005.9
Exp/Cntr=0.3,0.1

Type RM Length L Ch R = 1,39942,449,449,449
BEGIN DESCRIPTION:
Stream0146 25.0
END DESCRIPTION:
XS GIS Cut Line= 3
      1788524.99     13908824.99      1788675.00     13909025.00
      1788824.99     13909424.98
#Sta/Elev= 30
  4750.0 2209.54  4800.0 2207.33  4828.1 2204.85  4871.9 2202.86  4878.1 2201.83
  4950.0 2198.59  4963.6 2197.67  4996.9 2193.56  5002.7 2193.56  5006.0 2192.71
  5006.5 2192.21  5013.2 2192.21  5013.7 2192.71  5015.1 2193.35  5021.4 2193.04
  5040.1 2193.97  5064.1 2196.35  5070.3 2195.91  5100.6 2199.13  5138.9 2200.97
  5161.1 2203.69  5210.9 2206.43  5216.3 2207.56  5235.0 2209.31  5246.5 2211.46
  5293.5 2216.11  5332.0 2220.67  5351.6 2221.69  5383.8 2224.74  5427.2 2230.14
#Mann=5,-1,0
  4750.0     0.1       0  5006.0    0.05       0  5013.7     0.1       0
  5293.5    0.07       0  5383.8     0.1       0
Bank Sta=5006,5013.7
Exp/Cntr=0.3,0.1

Type RM Length L Ch R = 1,39493,468,468,468
BEGIN DESCRIPTION:
Stream0146 24.0
END DESCRIPTION:
XS GIS Cut Line= 3
      1788174.97     13909174.97      1788425.00     13909375.00
      1788775.01     13909525.01
#Sta/Elev= 30
  4684.2 2207.42  4726.7 2206.50  4790.7 2203.28  4834.9 2202.05  4876.3 2201.70
  4918.8 2199.94  4940.4 2196.03  4954.0 2194.79  4962.0 2193.12  4976.4 2191.71
  4986.9 2191.57  4987.4 2191.07  4994.2 2191.07  4994.7 2191.57  5037.0 2193.68
  5058.8 2195.52  5066.0 2196.76  5071.5 2196.79  5102.3 2201.25  5135.0 2203.91
  5165.8 2208.92  5178.5 2209.63  5200.2 2212.98  5247.4 2218.69  5265.5 2220.00
  5276.4 2222.08  5300.0 2225.27  5352.5 2229.92  5370.7 2232.49  5385.2 2233.60
#Mann=4,-1,0
  4684.2    0.07       0  4834.9     0.1       0  4986.9    0.05       0
  4994.7     0.1       0
Bank Sta=4986.9,4994.7
Exp/Cntr=0.3,0.1

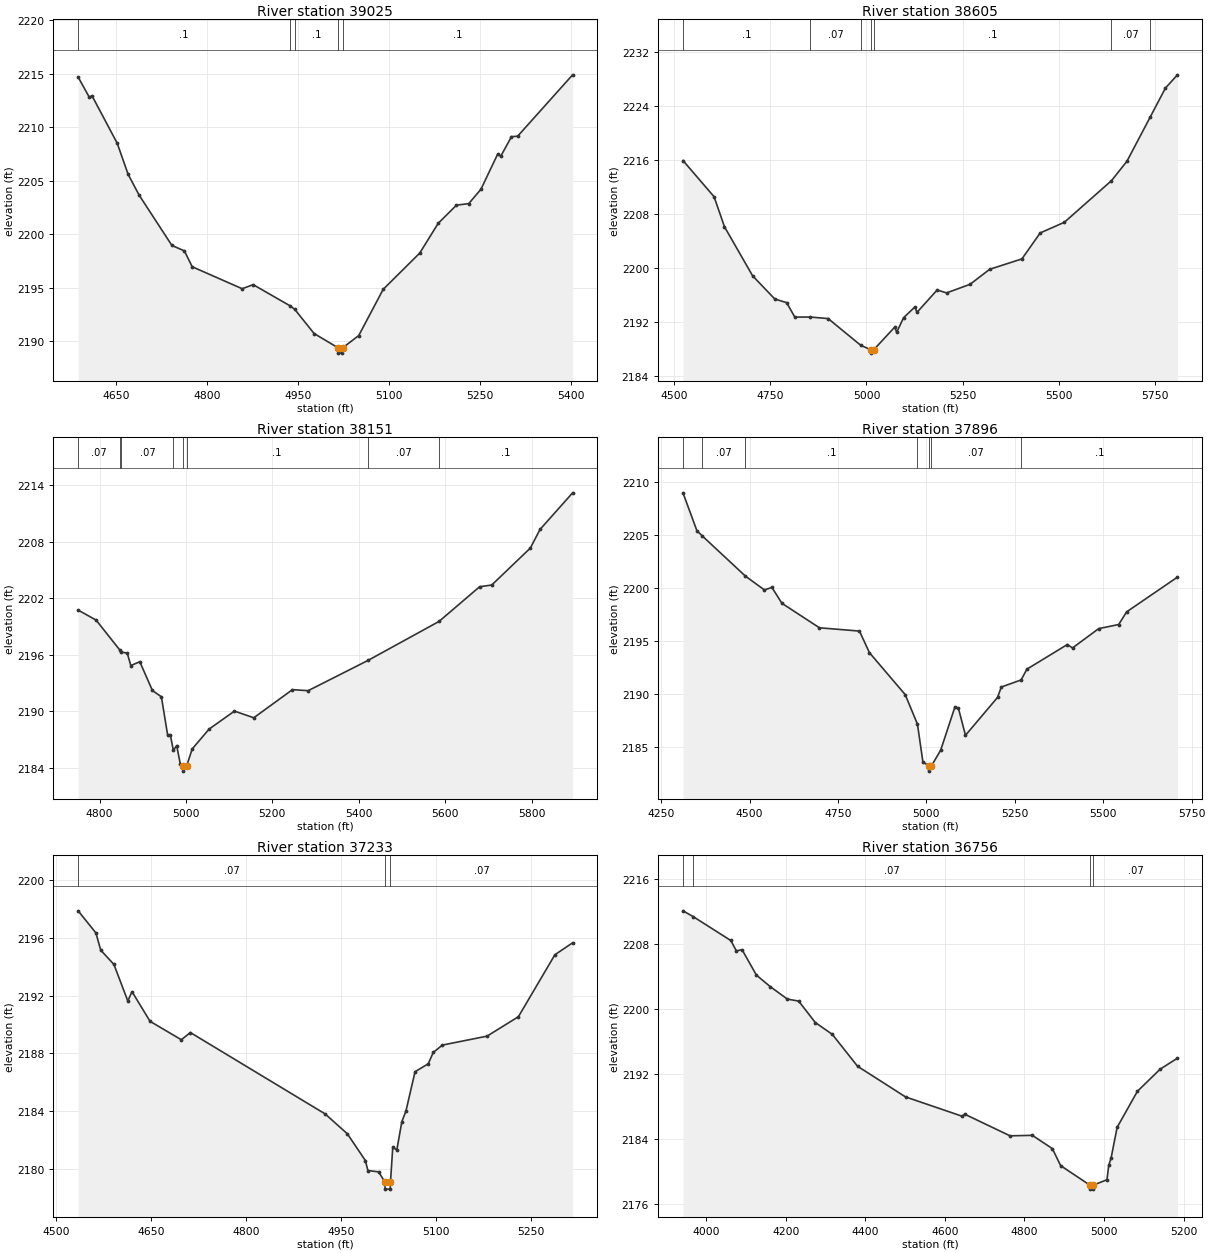
Type RM Length L Ch R = 1,39025,420,420,420
BEGIN DESCRIPTION:
Stream0146 23.0
END DESCRIPTION:
XS GIS Cut Line= 3
      1787825.03     13909675.01      1788225.00     13909775.00
      1788625.01     13909725.00
#Sta/Elev= 30
  4587.7 2214.67  4605.7 2212.83  4610.9 2212.89  4652.1 2208.50  4670.1 2205.60
  4688.2 2203.66  4742.3 2198.96  4762.9 2198.45  4775.8 2196.97  4858.2 2194.92
  4876.3 2195.30  4937.0 2193.33  4944.8 2193.00  4976.8 2190.74  5016.2 2189.41
  5016.7 2188.91  5023.5 2188.91  5024.0 2189.41  5050.4 2190.55  5090.7 2194.86
  5151.1 2198.25  5181.4 2201.02  5211.6 2202.72  5231.8 2202.86  5251.9 2204.20
  5279.6 2207.49  5284.7 2207.29  5302.3 2209.11  5312.4 2209.15  5403.1 2214.88
#Mann=5,-1,0
  4587.7     0.1       0  4937.0    0.07       0  4944.8     0.1       0
  5016.2    0.05       0  5024.0     0.1       0
Bank Sta=5016.2,5024
Exp/Cntr=0.3,0.1

Type RM Length L Ch R = 1,38605,454,454,454
BEGIN DESCRIPTION:
Stream0146 22.0
END DESCRIPTION:
XS GIS Cut Line= 3
      1787775.00     13909725.01      1788025.00     13910125.00
      1788824.97     13909975.01
#Sta/Elev= 30
  4523.0 2215.87  4603.8 2210.52  4630.9 2206.07  4704.0 2198.82  4761.8 2195.38
  4792.5 2194.85  4813.7 2192.71  4854.0 2192.72  4900.4 2192.49  4984.9 2188.55
  5011.1 2187.88  5011.6 2187.38  5019.0 2187.88  5073.5 2191.23  5078.6 2190.46
  5096.4 2192.61  5126.1 2194.22  5131.2 2193.40  5183.8 2196.72  5208.4 2196.29
  5269.4 2197.56  5320.3 2199.78  5404.2 2201.32  5451.7 2205.16  5514.4 2206.73
  5637.0 2212.89  5677.2 2215.76  5737.9 2222.32  5777.3 2226.59  5808.6 2228.55
#Mann=7,-1,0
  4523.0     0.1       0  4854.0    0.07       0  4984.9     0.1       0
  5011.1    0.05       0  5019.0     0.1       0  5637.0    0.07       0
  5737.9     0.1       0
Bank Sta=5011.1,5019
Exp/Cntr=0.3,0.1

Type RM Length L Ch R = 1,38151,255,255,255
BEGIN DESCRIPTION:
Stream0146 21.0
END DESCRIPTION:
XS GIS Cut Line= 3
      1787674.99     13910374.99      1787875.00     13910525.00
      1788674.97     13910125.02
#Sta/Elev= 30
  4750.5 2200.76  4792.2 2199.69  4846.6 2196.53  4850.6 2196.29  4864.1 2196.19
  4872.4 2194.86  4893.2 2195.27  4922.4 2192.21  4943.2 2191.54  4957.8 2187.43
  4964.1 2187.44  4970.9 2185.84  4978.6 2186.36  4987.0 2184.38  4993.4 2184.14
  4993.9 2183.64  5001.3 2184.14  5014.5 2186.00  5053.6 2188.11  5112.3 2190.02
  5157.0 2189.31  5246.5 2192.30  5282.8 2192.19  5421.1 2195.40  5585.7 2199.55
  5679.7 2203.24  5707.7 2203.42  5797.1 2207.35  5819.5 2209.33  5894.9 2213.22
#Mann=8,-1,0
  4750.5    0.07       0  4846.6     0.1       0  4850.6    0.07       0
  4970.9     0.1       0  4993.4    0.05       0  5001.3     0.1       0
  5421.1    0.07       0  5585.7     0.1       0
Bank Sta=4993.4,5001.3
Exp/Cntr=0.3,0.1

Type RM Length L Ch R = 1,37896,663,663,663
BEGIN DESCRIPTION:
Stream0146 20.1
END DESCRIPTION:
XS GIS Cut Line= 4
      1787411.46     13910352.97      1787825.34     13910771.28
      1788107.20     13910751.11      1788615.13     13910610.75
#Sta/Elev= 30
  4311.9 2209.01  4351.2 2205.44  4365.3 2204.98  4488.2 2201.16  4542.1 2199.85
  4563.3 2200.09  4591.6 2198.59  4697.7 2196.28  4810.8 2195.97  4839.1 2193.93
  4940.1 2189.98  4974.8 2187.19  4990.2 2183.63  5006.1 2183.26  5006.6 2182.76
  5014.4 2183.26  5040.4 2184.73  5080.5 2188.79  5090.5 2188.70  5110.6 2186.14
  5201.4 2189.72  5211.8 2190.69  5267.7 2191.36  5284.4 2192.38  5398.5 2194.70
  5413.2 2194.38  5487.1 2196.20  5543.8 2196.59  5566.1 2197.78  5709.9 2201.06
#Mann=7,-1,0
  4311.9     0.1       0  4365.3    0.07       0  4488.2     0.1       0
  4974.8    0.07       0  5006.1    0.05       0  5014.4    0.07       0
  5267.7     0.1       0
Bank Sta=5006.1,5014.4
Exp/Cntr=0.3,0.1

Type RM Length L Ch R = 1,37233,477,477,477
BEGIN DESCRIPTION:
Stream0146 20.0
END DESCRIPTION:
XS GIS Cut Line= 3
      1787675.00     13911025.00      1788025.00     13911325.00
      1788274.98     13911524.98
#Sta/Elev= 30
  4534.6 2197.89  4562.6 2196.36  4570.3 2195.16  4591.1 2194.17  4613.1 2191.63
  4619.7 2192.28  4648.2 2190.22  4697.6 2188.94  4711.9 2189.44  4924.8 2183.79
  4959.9 2182.41  4988.4 2180.55  4992.3 2179.86  5009.2 2179.77  5019.1 2179.07
  5019.6 2178.57  5027.5 2178.57  5028.0 2179.07  5031.6 2181.47  5038.0 2181.29
  5046.0 2183.26  5052.4 2183.99  5066.8 2186.72  5087.6 2187.27  5095.6 2188.06
  5110.0 2188.57  5180.5 2189.19  5230.1 2190.54  5287.7 2194.84  5315.7 2195.67
#Mann=3,-1,0
  4534.6    0.07       0  5019.1    0.05       0  5028.0    0.07       0
Bank Sta=5019.1,5028
Exp/Cntr=0.3,0.1

Type RM Length L Ch R = 1,36756,445,445,445
BEGIN DESCRIPTION:
Stream0146 19.0
END DESCRIPTION:
XS GIS Cut Line= 3
      1787225.00     13910974.99      1787925.00     13911775.00
      1788075.00     13911875.00
#Sta/Elev= 30
  3941.5 2212.09  3967.4 2211.37  4061.6 2208.44  4075.8 2207.16  4090.0 2207.31
  4126.1 2204.18  4161.2 2202.75  4203.9 2201.23  4232.4 2200.98  4274.2 2198.34
  4316.9 2196.89  4380.5 2192.96  4501.0 2189.19  4643.4 2186.81  4650.0 2187.06
  4763.9 2184.40  4819.9 2184.46  4870.2 2182.83  4891.1 2180.73  4964.4 2178.34
  4964.9 2177.84  4972.9 2177.84  4973.4 2178.34  5007.5 2178.99  5012.0 2180.75
  5018.0 2181.69  5033.1 2185.44  5084.1 2189.88  5141.2 2192.60  5184.8 2193.96
#Mann=4,-1,0
  3941.5     0.1       0  3967.4    0.07       0  4964.4    0.05       0
  4973.4    0.07       0
Bank Sta=4964.4,4973.4
Exp/Cntr=0.3,0.1

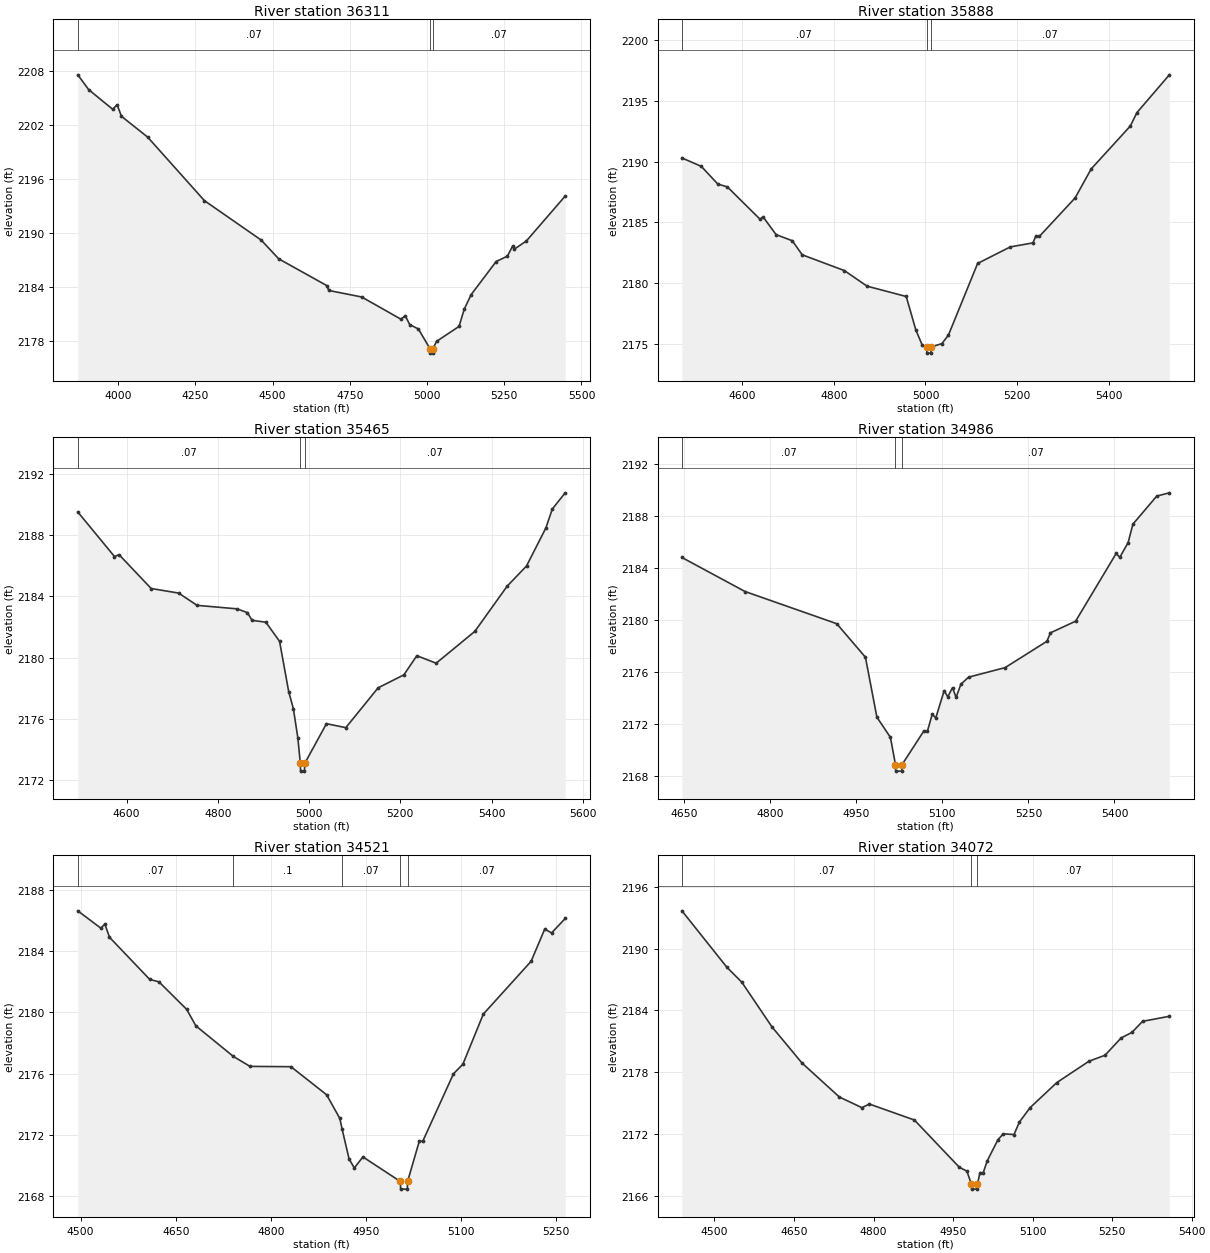
Type RM Length L Ch R = 1,36311,423,423,423
BEGIN DESCRIPTION:
Stream0146 18.0
END DESCRIPTION:
XS GIS Cut Line= 3
      1786824.98     13911274.98      1787625.00     13912075.00
      1787824.99     13912474.98
#Sta/Elev= 30
  3868.8 2207.52  3904.2 2205.87  3982.0 2203.69  3996.1 2204.20  4010.3 2202.91
  4095.1 2200.60  4279.0 2193.54  4462.8 2189.16  4519.4 2187.08  4674.9 2184.11
  4682.0 2183.56  4788.1 2182.84  4915.4 2180.37  4929.5 2180.76  4943.6 2179.78
  4971.9 2179.28  5009.4 2177.10  5009.9 2176.60  5018.4 2176.60  5018.9 2177.10
  5030.9 2177.91  5103.6 2179.57  5120.4 2181.48  5142.8 2183.10  5223.8 2186.78
  5260.1 2187.37  5276.9 2188.48  5282.5 2188.15  5321.6 2189.06  5447.4 2194.05
#Mann=3,-1,0
  3868.8    0.07       0  5009.4    0.05       0  5018.9    0.07       0
Bank Sta=5009.4,5018.9
Exp/Cntr=0.3,0.1

Type RM Length L Ch R = 1,35888,423,423,423
BEGIN DESCRIPTION:
Stream0146 17.0
END DESCRIPTION:
XS GIS Cut Line= 3
      1786875.04     13911925.03      1787275.00     13912275.00
      1787625.02     13912675.02
#Sta/Elev= 30
  4468.8 2190.31  4511.0 2189.62  4547.1 2188.16  4567.9 2187.93  4639.1 2185.27
  4645.8 2185.46  4674.2 2184.00  4709.4 2183.50  4731.2 2182.34  4823.2 2181.04
  4872.6 2179.76  4958.0 2178.91  4978.9 2176.16  4993.1 2174.89  5002.6 2174.75
  5003.1 2174.25  5011.7 2174.25  5012.2 2174.75  5035.9 2175.04  5050.1 2175.74
  5113.7 2181.63  5184.9 2182.99  5234.2 2183.32  5240.9 2183.90  5248.5 2183.86
  5326.3 2187.02  5361.4 2189.41  5446.8 2192.94  5461.1 2194.04  5531.8 2197.15
#Mann=3,-1,0
  4468.8    0.07       0  5002.6    0.05       0  5012.2    0.07       0
Bank Sta=5002.6,5012.2
Exp/Cntr=0.3,0.1

Type RM Length L Ch R = 1,35465,479,479,479
BEGIN DESCRIPTION:
Stream0146 16.0
END DESCRIPTION:
XS GIS Cut Line= 3
      1786875.00     13911974.95      1786925.00     13912475.00
      1787324.98     13912874.98
#Sta/Elev= 30
  4493.1 2189.52  4573.5 2186.61  4583.6 2186.73  4653.9 2184.52  4714.2 2184.22
  4754.4 2183.42  4842.4 2183.19  4865.0 2182.94  4875.0 2182.44  4905.2 2182.32
  4935.3 2181.07  4955.4 2177.77  4965.5 2176.68  4975.5 2174.74  4980.8 2173.09
  4981.3 2172.59  4989.9 2172.59  4990.4 2173.09  5038.1 2175.69  5080.5 2175.43
  5151.2 2178.03  5207.8 2178.88  5236.1 2180.13  5278.5 2179.64  5363.3 2181.72
  5434.0 2184.67  5476.5 2185.99  5518.9 2188.47  5533.0 2189.71  5561.3 2190.77
#Mann=3,-1,0
  4493.1    0.07       0  4980.8    0.05       0  4990.4    0.07       0
Bank Sta=4980.8,4990.4
Exp/Cntr=0.3,0.1

Type RM Length L Ch R = 1,34986,465,465,465
BEGIN DESCRIPTION:
Stream0146 15.0
END DESCRIPTION:
XS GIS Cut Line= 3
      1786374.98     13912875.00      1786725.00     13912875.00
      1787124.99     13913174.99
#Sta/Elev= 30
  4645.7 2184.80  4755.7 2182.19  4915.7 2179.72  4965.7 2177.15  4985.7 2172.55
  5009.3 2171.00  5018.1 2168.91  5018.6 2168.41  5029.1 2168.41  5029.6 2168.91
  5067.6 2171.49  5073.8 2171.47  5082.2 2172.77  5088.4 2172.49  5103.0 2174.58
  5109.3 2174.11  5117.6 2174.81  5123.8 2174.06  5132.2 2175.08  5145.7 2175.62
  5209.3 2176.35  5282.2 2178.37  5288.4 2179.02  5332.2 2179.91  5403.0 2185.11
  5409.3 2184.81  5423.8 2185.94  5432.2 2187.36  5473.8 2189.51  5495.7 2189.76
#Mann=3,-1,0
  4645.7    0.07       0  5018.1    0.05       0  5029.6    0.07       0
Bank Sta=5018.1,5029.6
Exp/Cntr=0.3,0.1

Type RM Length L Ch R = 1,34521,449,449,449
BEGIN DESCRIPTION:
Stream0146 14.0
END DESCRIPTION:
XS GIS Cut Line= 3
      1786275.03     13913025.02      1786675.00     13913325.00
      1786924.98     13913424.99
#Sta/Elev= 30
  4495.5 2186.61  4531.9 2185.48  4538.2 2185.75  4545.5 2184.89  4609.0 2182.14
  4623.6 2181.98  4667.3 2180.19  4681.9 2179.11  4741.0 2177.12  4767.3 2176.47
  4831.9 2176.45  4888.2 2174.62  4909.0 2173.08  4912.6 2172.39  4923.6 2170.44
  4931.9 2169.85  4945.5 2170.57  5004.5 2168.97  5005.0 2168.47  5015.5 2168.47
  5016.0 2168.97  5034.5 2171.60  5039.9 2171.59  5088.4 2175.99  5103.2 2176.61
  5135.5 2179.88  5210.9 2183.32  5232.4 2185.42  5243.2 2185.17  5264.7 2186.11
#Mann=5,-1,0
  4495.5    0.07       0  4741.0     0.1       0  4912.6    0.07       0
  5004.5    0.05       0  5016.0    0.07       0
Bank Sta=5004.5,5016
Exp/Cntr=0.3,0.1

Type RM Length L Ch R = 1,34072,452,452,452
BEGIN DESCRIPTION:
Stream0146 13.0
END DESCRIPTION:
XS GIS Cut Line= 3
      1786125.01     13913325.01      1786525.00     13913725.00
      1786874.98     13913675.00
#Sta/Elev= 30
  4438.7 2193.66  4523.5 2188.18  4551.8 2186.72  4608.4 2182.40  4665.0 2178.89
  4735.7 2175.58  4778.1 2174.55  4792.2 2174.90  4877.1 2173.35  4961.9 2168.76
  4976.1 2168.39  4984.5 2167.14  4985.0 2166.64  4995.5 2166.64  4996.0 2167.14
  5000.8 2168.23  5006.9 2168.23  5014.5 2169.39  5034.7 2171.44  5044.8 2172.01
  5065.0 2171.94  5075.1 2173.15  5095.3 2174.55  5145.8 2176.99  5206.4 2179.06
  5236.7 2179.64  5267.0 2181.32  5287.2 2181.85  5307.4 2182.93  5357.9 2183.42
#Mann=3,-1,0
  4438.7    0.07       0  4984.5    0.05       0  4996.0    0.07       0
Bank Sta=4984.5,4996
Exp/Cntr=0.3,0.1

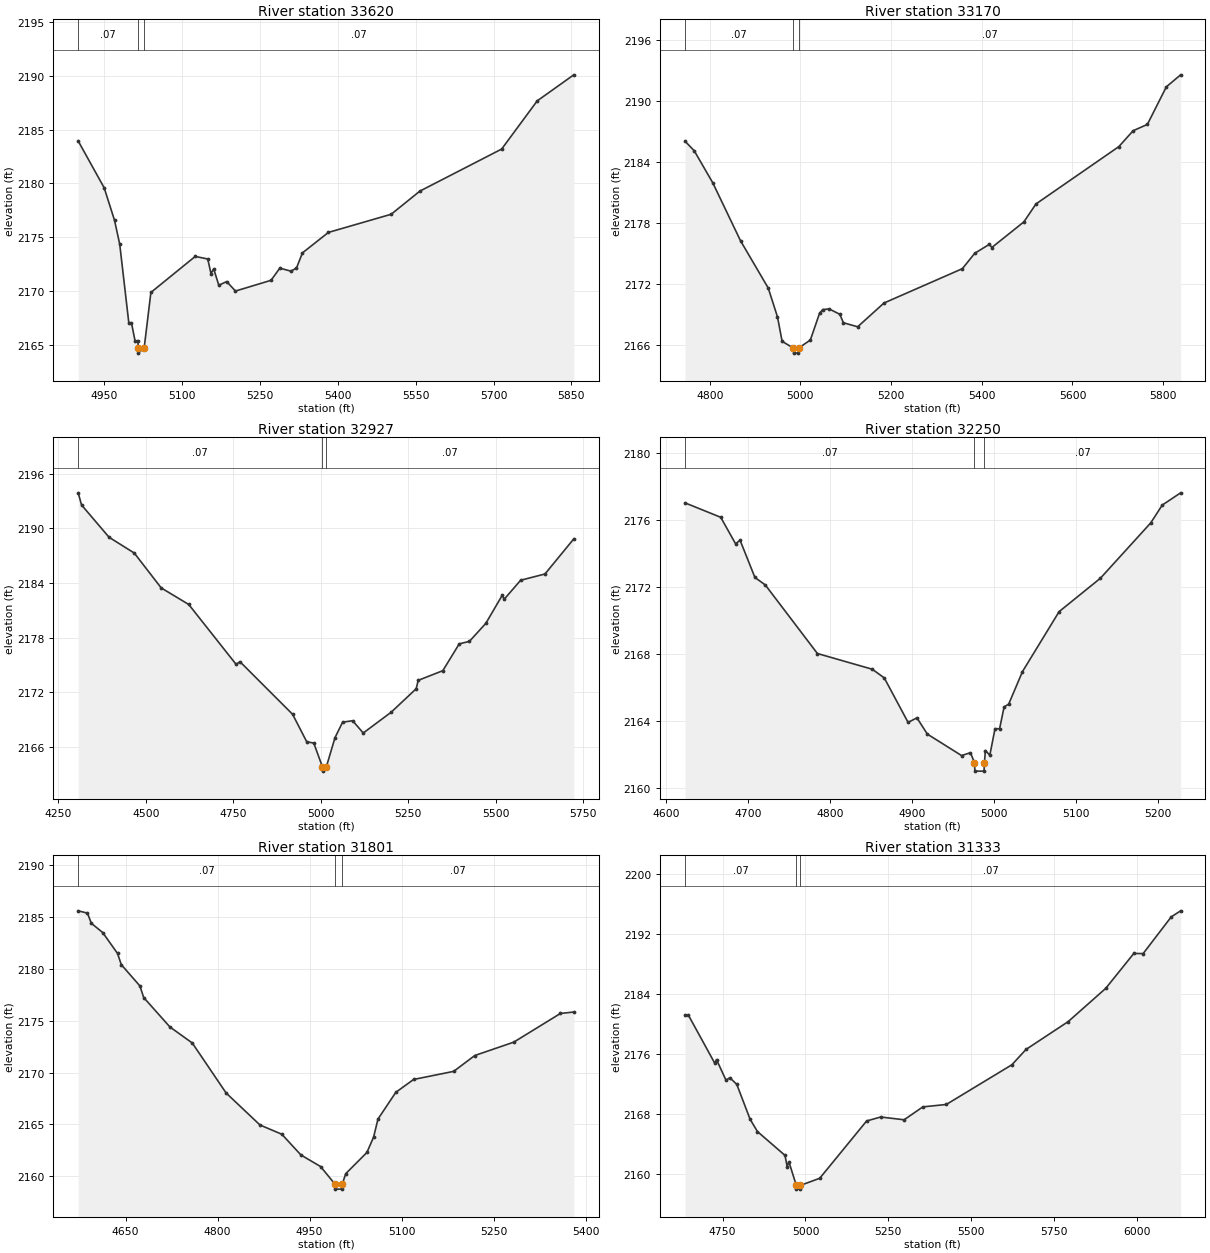
Type RM Length L Ch R = 1,33620,450,450,450
BEGIN DESCRIPTION:
Stream0146 12.0
END DESCRIPTION:
XS GIS Cut Line= 3
      1786175.04     13914075.00      1786275.00     13914075.00
      1787075.04     13913774.98
#Sta/Elev= 30
  4900.2 2183.94  4950.2 2179.59  4970.2 2176.56  4980.2 2174.34  4997.7 2167.03
  5002.8 2167.03  5009.9 2165.31  5015.3 2165.39  5015.7 2164.72  5016.2 2164.22
  5027.3 2164.72  5040.2 2169.86  5125.6 2173.21  5149.7 2172.97  5155.9 2171.62
  5161.2 2172.04  5171.0 2170.53  5186.2 2170.87  5203.1 2169.99  5271.6 2170.99
  5288.5 2172.12  5309.9 2171.84  5320.6 2172.13  5332.1 2173.54  5382.0 2175.44
  5503.0 2177.13  5558.2 2179.28  5715.7 2183.19  5784.2 2187.67  5854.6 2190.09
#Mann=3,-1,0
  4900.2    0.07       0  5015.7    0.05       0  5027.3    0.07       0
Bank Sta=5015.7,5027.3
Exp/Cntr=0.3,0.1

Type RM Length L Ch R = 1,33170,243,243,243
BEGIN DESCRIPTION:
Stream0146 11.0
END DESCRIPTION:
XS GIS Cut Line= 3
      1786175.02     13914425.00      1786425.00     13914475.00
      1787225.02     13914224.99
#Sta/Elev= 30
  4745.5 2186.09  4765.9 2185.14  4806.7 2181.99  4867.9 2176.29  4929.0 2171.64
  4949.4 2168.80  4959.6 2166.40  4984.4 2165.74  4984.9 2165.24  4995.5 2165.24
  4996.0 2165.74  5021.9 2166.53  5042.3 2169.18  5049.1 2169.52  5063.3 2169.59
  5086.9 2169.06  5094.7 2168.23  5126.2 2167.83  5184.3 2170.17  5357.2 2173.55
  5384.4 2175.06  5416.9 2175.95  5422.1 2175.63  5492.8 2178.15  5519.6 2179.92
  5702.4 2185.56  5733.8 2187.12  5765.2 2187.74  5807.1 2191.44  5838.6 2192.62
#Mann=3,-1,0
  4745.5    0.07       0  4984.4    0.05       0  4996.0    0.07       0
Bank Sta=4984.4,4996
Exp/Cntr=0.3,0.1

Type RM Length L Ch R = 1,32927,677,677,677
BEGIN DESCRIPTION:
Stream0146 10.1
END DESCRIPTION:
XS GIS Cut Line= 4
      1785928.99     13914436.89      1786278.64     13914711.84
      1786825.20     13914636.72      1787210.60     13914470.27
#Sta/Elev= 30
  4306.9 2193.92  4316.4 2192.59  4395.0 2189.04  4467.2 2187.30  4544.1 2183.47
  4622.8 2181.65  4758.1 2175.07  4769.2 2175.36  4919.6 2169.58  4960.0 2166.56
  4980.2 2166.41  5004.6 2163.83  5005.1 2163.33  5016.3 2163.83  5040.8 2167.01
  5062.5 2168.71  5091.2 2168.87  5121.5 2167.52  5201.5 2169.81  5272.9 2172.39
  5278.6 2173.31  5348.9 2174.37  5395.9 2177.32  5424.8 2177.59  5471.8 2179.57
  5518.9 2182.67  5524.3 2182.22  5571.3 2184.31  5640.9 2185.00  5723.2 2188.86
#Mann=3,-1,0
  4306.9    0.07       0  5004.6    0.05       0  5016.3    0.07       0
Bank Sta=5004.6,5016.3
Exp/Cntr=0.3,0.1

Type RM Length L Ch R = 1,32250,449,449,449
BEGIN DESCRIPTION:
Stream0146 10.0
END DESCRIPTION:
XS GIS Cut Line= 3
      1786575.03     13915324.99      1786925.00     13915175.00
      1787125.03     13915074.99
#Sta/Elev= 30
  4623.3 2177.04  4666.8 2176.18  4684.9 2174.60  4690.4 2174.81  4708.5 2172.59
  4721.2 2172.14  4784.7 2168.05  4851.7 2167.11  4866.3 2166.59  4895.3 2163.94
  4906.1 2164.21  4918.8 2163.24  4960.5 2161.96  4971.4 2162.13  4976.3 2161.53
  4976.8 2161.03  4987.9 2161.03  4988.4 2161.53  4989.6 2162.26  4995.0 2161.98
  5001.3 2163.56  5006.9 2163.56  5012.4 2164.86  5018.0 2165.03  5034.8 2166.97
  5079.5 2170.55  5129.8 2172.54  5191.3 2175.85  5205.3 2176.91  5227.7 2177.64
#Mann=3,-1,0
  4623.3    0.07       0  4976.3    0.05       0  4988.4    0.07       0
Bank Sta=4976.3,4988.4
Exp/Cntr=0.3,0.1

Type RM Length L Ch R = 1,31801,468,468,468
BEGIN DESCRIPTION:
Stream0146 9.0
END DESCRIPTION:
XS GIS Cut Line= 3
      1786525.00     13915775.00      1786925.00     13915625.00
      1787275.01     13915474.99
#Sta/Elev= 30
  4572.8 2185.62  4587.9 2185.40  4594.2 2184.42  4612.8 2183.52  4636.9 2181.51
  4643.1 2180.42  4673.4 2178.37  4679.6 2177.25  4722.3 2174.41  4758.8 2172.86
  4814.0 2168.03  4869.2 2164.94  4904.8 2164.05  4935.9 2162.05  4968.0 2160.93
  4991.2 2159.25  4991.7 2158.75  5002.9 2158.75  5003.4 2159.25  5009.1 2160.25
  5043.5 2162.29  5054.4 2163.77  5061.6 2165.52  5090.7 2168.10  5119.7 2169.34
  5185.0 2170.12  5219.4 2171.65  5282.9 2172.94  5359.0 2175.71  5380.8 2175.85
#Mann=3,-1,0
  4572.8    0.07       0  4991.2    0.05       0  5003.4    0.07       0
Bank Sta=4991.2,5003.4
Exp/Cntr=0.3,0.1

Type RM Length L Ch R = 1,31333,430,430,430
BEGIN DESCRIPTION:
Stream0146 8.0
END DESCRIPTION:
XS GIS Cut Line= 3
      1786625.03     13915975.01      1786975.00     13916075.00
      1787774.97     13915275.03
#Sta/Elev= 30
  4636.6 2181.26  4647.0 2181.20  4726.3 2174.81  4731.5 2175.30  4760.1 2172.55
  4771.8 2172.87  4792.6 2172.00  4832.9 2167.34  4855.0 2165.70  4938.2 2162.52
  4944.7 2161.02  4949.9 2161.67  4972.3 2158.52  4972.8 2158.02  4984.2 2158.02
  4984.7 2158.52  5043.0 2159.47  5184.4 2167.11  5226.8 2167.64  5297.6 2167.27
  5354.1 2168.99  5424.8 2169.31  5622.8 2174.61  5665.3 2176.65  5792.5 2180.36
  5905.7 2184.79  5990.5 2189.45  6018.8 2189.44  6103.7 2194.34  6131.9 2195.14
#Mann=3,-1,0
  4636.6    0.07       0  4972.3    0.05       0  4984.7    0.07       0
Bank Sta=4972.3,4984.7
Exp/Cntr=0.3,0.1