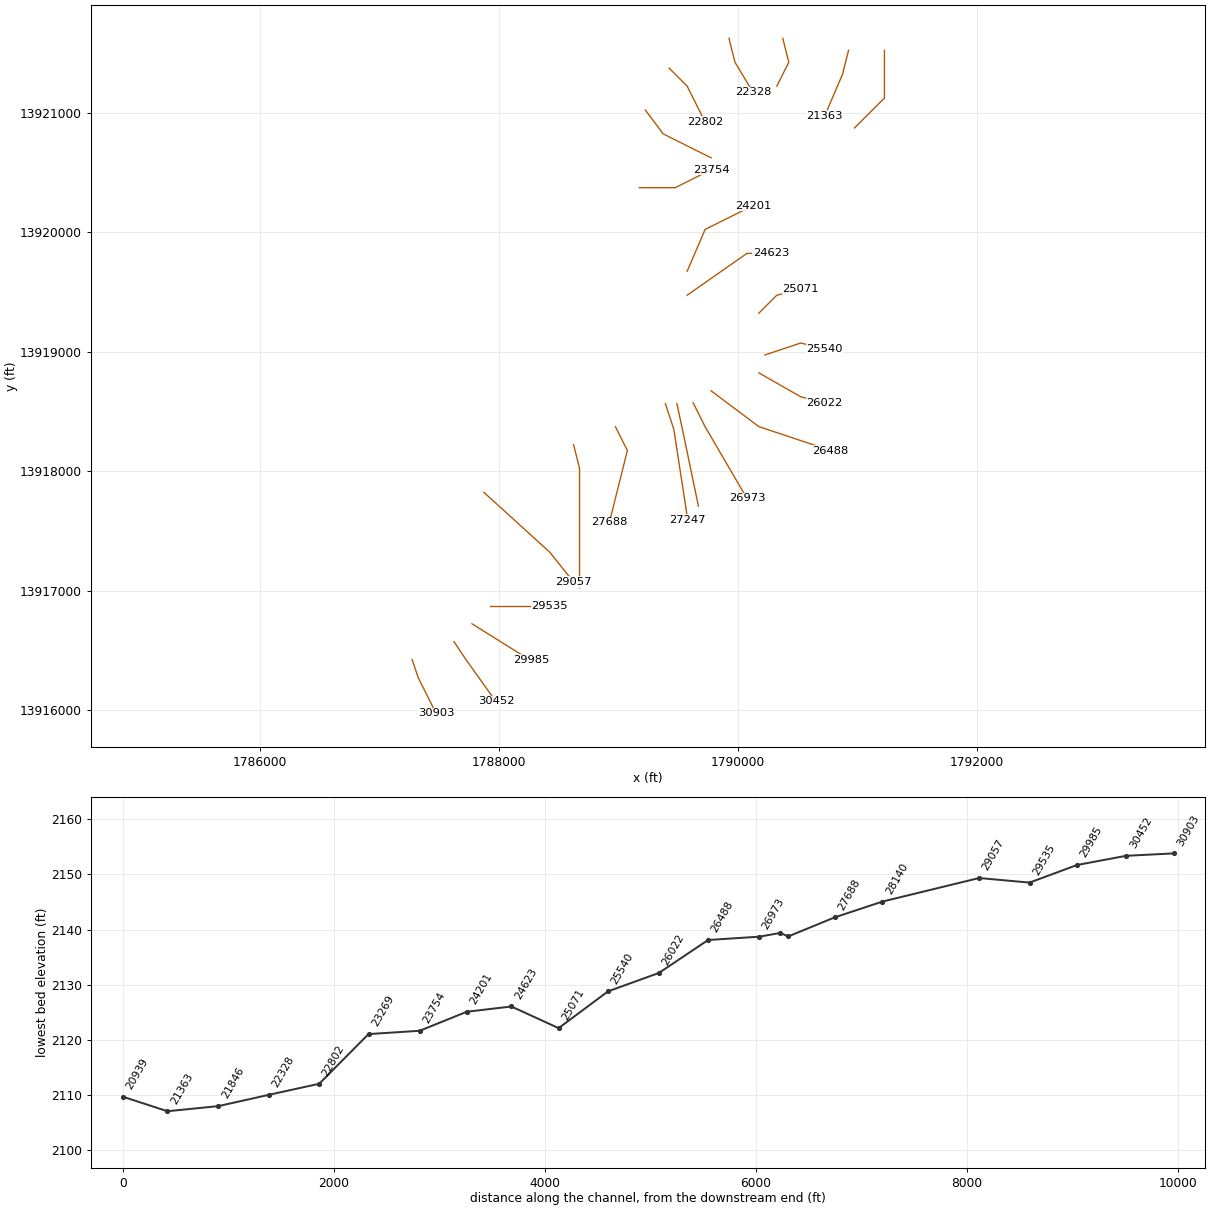
HEC-RAS study Flat Rock Creek 2.prj: Flat Rock Creek 2 Base Level Engineering

--- Flat Rock Creek 2.g01 (geometry) --- (continued)

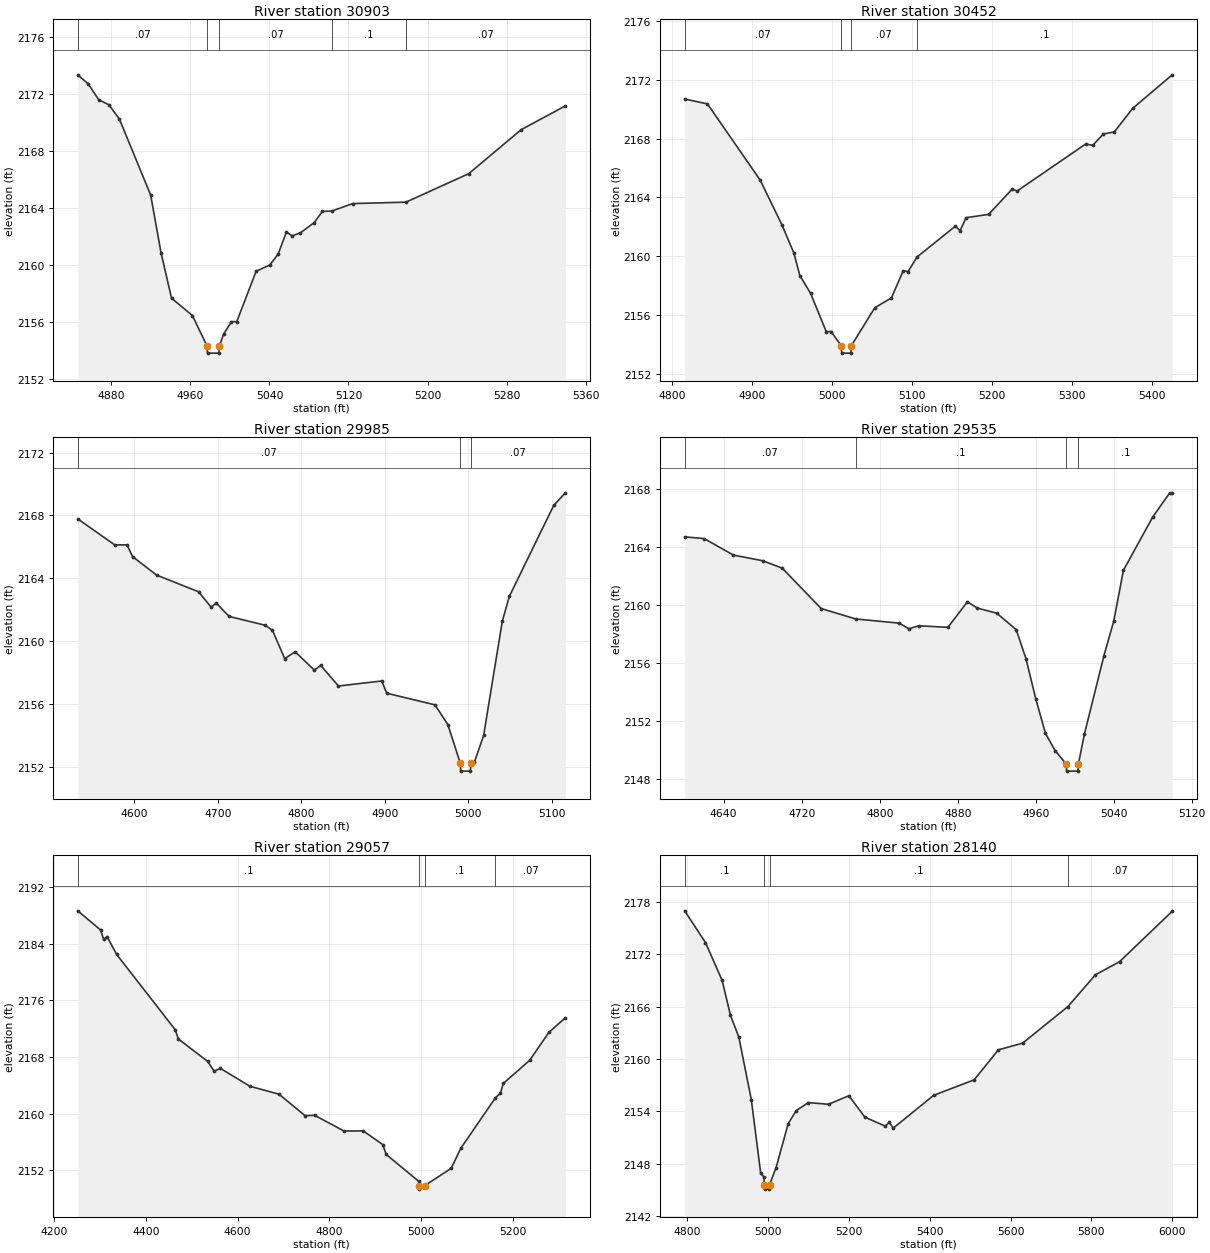
Type RM Length L Ch R = 1,30903,451,451,451
BEGIN DESCRIPTION:
Stream0146 7.0
END DESCRIPTION:
XS GIS Cut Line= 3
      1787274.99     13916425.02      1787325.00     13916275.00
      1787474.98     13915975.04
#Sta/Elev= 30
  4846.0 2173.36  4856.6 2172.72  4867.1 2171.62  4877.6 2171.25  4888.2 2170.24
  4919.8 2164.91  4930.3 2160.85  4940.9 2157.68  4962.0 2156.46  4976.8 2154.32
  4977.3 2153.82  4988.8 2153.82  4989.3 2154.32  4993.6 2155.15  5001.5 2156.03
  5006.9 2156.03  5026.5 2159.57  5040.5 2160.01  5048.9 2160.79  5057.2 2162.33
  5062.8 2162.05  5071.2 2162.26  5085.2 2162.98  5093.6 2163.77  5103.3 2163.80
  5124.3 2164.32  5178.2 2164.42  5241.7 2166.42  5294.8 2169.51  5339.5 2171.18
#Mann=5,-1,0
  4846.0    0.07       0  4976.8    0.05       0  4989.3    0.07       0
  5103.3     0.1       0  5178.2    0.07       0
Bank Sta=4976.8,4989.3
Exp/Cntr=0.3,0.1

Type RM Length L Ch R = 1,30452,467,467,467
BEGIN DESCRIPTION:
Stream0146 6.0
END DESCRIPTION:
XS GIS Cut Line= 3
      1787625.02     13916574.97      1787725.00     13916425.00
      1787975.02     13916074.97
#Sta/Elev= 30
  4815.5 2170.71  4844.0 2170.38  4910.1 2165.18  4937.2 2162.14  4952.2 2160.22
  4959.7 2158.68  4973.2 2157.46  4992.7 2154.86  4998.8 2154.86  5011.6 2153.89
  5012.1 2153.39  5023.6 2153.39  5024.1 2153.89  5053.5 2156.48  5074.4 2157.16
  5089.1 2159.00  5095.3 2158.95  5106.4 2159.94  5154.3 2162.04  5160.4 2161.74
  5167.8 2162.62  5196.1 2162.85  5225.5 2164.57  5231.7 2164.44  5317.7 2167.65
  5326.3 2167.55  5339.8 2168.33  5353.4 2168.47  5376.7 2170.09  5425.9 2172.36
#Mann=4,-1,0
  4815.5    0.07       0  5011.6    0.05       0  5024.1    0.07       0
  5106.4     0.1       0
Bank Sta=5011.6,5024.1
Exp/Cntr=0.3,0.1

Type RM Length L Ch R = 1,29985,450,450,450
BEGIN DESCRIPTION:
Stream0146 5.0
END DESCRIPTION:
XS GIS Cut Line= 3
      1787774.96     13916725.02      1788175.00     13916475.00
      1788274.96     13916425.02
#Sta/Elev= 30
  4532.5 2167.78  4576.8 2166.12  4591.5 2166.13  4598.0 2165.38  4626.9 2164.20
  4677.0 2163.14  4692.3 2162.15  4698.2 2162.42  4713.6 2161.57  4756.6 2161.01
  4765.4 2160.69  4780.2 2158.88  4792.6 2159.32  4815.6 2158.15  4823.2 2158.45
  4844.5 2157.14  4896.3 2157.46  4902.2 2156.68  4960.0 2155.94  4975.4 2154.68
  4990.3 2152.22  4990.8 2151.72  5002.4 2151.72  5002.9 2152.22  5007.0 2152.27
  5018.2 2153.99  5040.6 2161.28  5049.0 2162.85  5102.1 2168.64  5116.0 2169.44
#Mann=3,-1,0
  4532.5    0.07       0  4990.3    0.05       0  5002.9    0.07       0
Bank Sta=4990.3,5002.9
Exp/Cntr=0.3,0.1

Type RM Length L Ch R = 1,29535,478,478,478
BEGIN DESCRIPTION:
Stream0146 4.0
END DESCRIPTION:
XS GIS Cut Line= 3
      1787925.00     13916875.00      1788325.00     13916875.00
      1788425.00     13916875.00
#Sta/Elev= 30
  4600.0 2164.71  4620.0 2164.59  4650.0 2163.45  4680.0 2163.06  4700.0 2162.55
  4740.0 2159.76  4775.3 2159.04  4820.0 2158.75  4830.0 2158.36  4840.0 2158.57
  4870.0 2158.46  4890.0 2160.23  4900.0 2159.79  4920.0 2159.44  4940.0 2158.30
  4950.0 2156.30  4960.0 2153.54  4970.0 2151.14  4980.0 2149.94  4991.2 2149.03
  4991.7 2148.53  5003.3 2148.53  5003.8 2149.03  5010.0 2151.10  5030.0 2156.51
  5040.0 2158.88  5050.0 2162.41  5080.0 2166.08  5097.5 2167.75  5100.0 2167.75
#Mann=4,-1,0
  4600.0    0.07       0  4775.3     0.1       0  4991.2    0.05       0
  5003.8     0.1       0
Bank Sta=4991.2,5003.8
Exp/Cntr=0.3,0.1

Type RM Length L Ch R = 1,29057,917,917,917
BEGIN DESCRIPTION:
Stream0146 3.0
END DESCRIPTION:
XS GIS Cut Line= 3
      1787874.98     13917825.02      1788425.00     13917325.00
      1788625.01     13917074.99
#Sta/Elev= 30
  4251.3 2188.64  4301.0 2185.94  4307.7 2184.61  4315.2 2185.01  4336.1 2182.48
  4463.8 2171.86  4470.6 2170.55  4534.8 2167.38  4548.6 2166.01  4562.5 2166.40
  4626.7 2163.88  4690.2 2162.76  4747.0 2159.73  4767.9 2159.78  4832.1 2157.56
  4874.0 2157.58  4916.6 2155.64  4924.0 2154.26  4994.6 2150.48  4995.4 2149.86
  4995.9 2149.36  5008.2 2149.86  5065.9 2152.30  5086.7 2155.12  5162.2 2162.24
  5173.1 2162.90  5179.5 2164.28  5237.1 2167.55  5278.8 2171.48  5314.8 2173.54
#Mann=4,-1,0
  4251.3     0.1       0  4995.4    0.05       0  5008.2     0.1       0
  5162.2    0.07       0
Bank Sta=4995.4,5008.2
Exp/Cntr=0.3,0.1

Type RM Length L Ch R = 1,28140,452,452,452
BEGIN DESCRIPTION:
Stream0146 2.0
END DESCRIPTION:
XS GIS Cut Line= 3
      1788625.01     13918224.96      1788675.00     13918025.00
      1788675.00     13917025.02
#Sta/Elev= 30
  4793.9 2177.00  4845.4 2173.36  4886.6 2169.02  4907.2 2165.02  4927.9 2162.52
  4958.8 2155.35  4982.0 2146.90  4989.7 2146.50  4991.0 2145.59  4991.5 2145.09
  5003.3 2145.09  5003.8 2145.59  5020.0 2147.54  5050.0 2152.60  5070.0 2154.10
  5100.0 2155.01  5150.0 2154.82  5200.0 2155.80  5240.0 2153.33  5290.0 2152.32
  5300.0 2152.74  5310.0 2152.09  5410.0 2155.85  5510.0 2157.62  5570.0 2161.06
  5630.0 2161.83  5741.7 2166.01  5810.0 2169.66  5870.0 2171.18  6000.0 2176.95
#Mann=4,-1,0
  4793.9     0.1       0  4991.0    0.05       0  5003.8     0.1       0
  5741.7    0.07       0
Bank Sta=4991,5003.8
Exp/Cntr=0.3,0.1

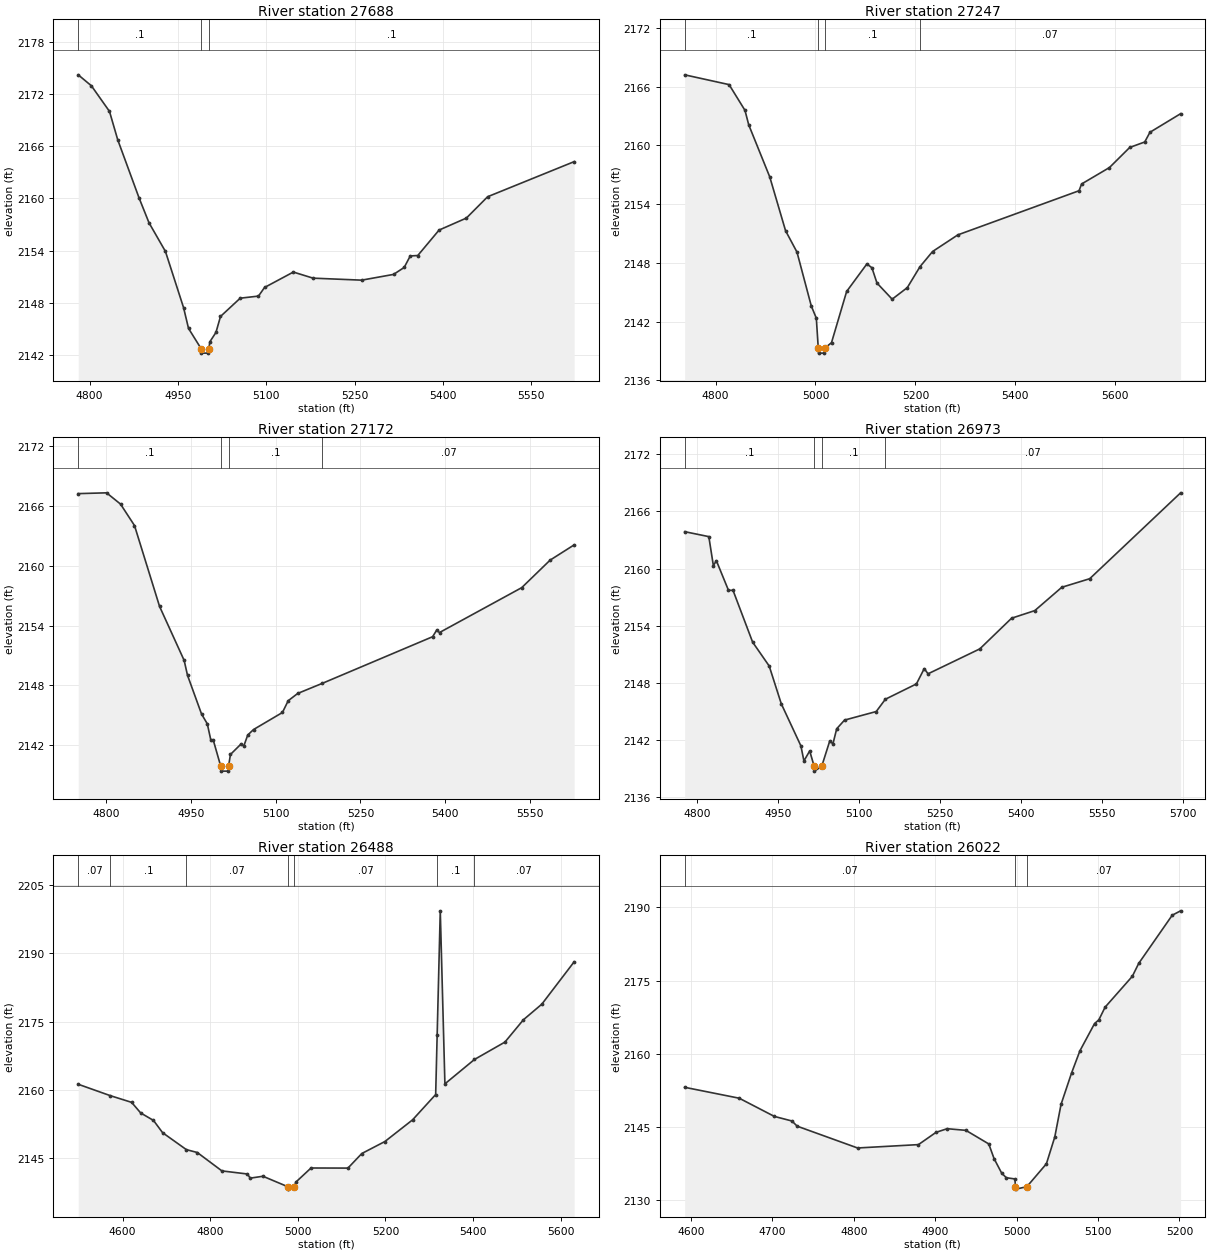
Type RM Length L Ch R = 1,27688,441,441,441
BEGIN DESCRIPTION:
Stream0146 1.0
END DESCRIPTION:
XS GIS Cut Line= 3
      1788975.00     13918375.00      1789075.00     13918175.00
      1788924.99     13917574.97
#Sta/Elev= 30
  4780.6 2174.19  4803.0 2172.93  4833.7 2169.99  4847.7 2166.73  4884.0 2160.04
  4900.8 2157.20  4928.7 2153.91  4959.5 2147.45  4967.9 2145.07  4989.4 2142.73
  4989.9 2142.23  5001.8 2142.23  5002.3 2142.73  5004.2 2143.54  5014.5 2144.61
  5022.2 2146.44  5055.7 2148.54  5086.7 2148.78  5097.0 2149.77  5145.9 2151.54
  5179.4 2150.84  5261.9 2150.61  5316.0 2151.27  5334.1 2152.07  5344.4 2153.39
  5357.2 2153.44  5393.3 2156.36  5439.7 2157.74  5475.8 2160.19  5622.7 2164.22
#Mann=3,-1,0
  4780.6     0.1       0  4989.4    0.05       0  5002.3     0.1       0
Bank Sta=4989.4,5002.3
Exp/Cntr=0.3,0.1

Type RM Length L Ch R = 1,27247,75,75,75
BEGIN DESCRIPTION:
Stream0146 0.0
END DESCRIPTION:
XS GIS Cut Line= 3
      1789392.95     13918566.77      1789463.26     13918353.23
      1789580.22     13917594.31
#Sta/Elev= 30
  4738.2 2167.20  4827.1 2166.20  4858.9 2163.57  4866.4 2162.09  4908.5 2156.77
  4940.1 2151.28  4963.0 2149.09  4991.6 2143.59  5001.7 2142.34  5005.6 2139.27
  5006.1 2138.77  5018.0 2138.77  5018.5 2139.27  5032.1 2139.84  5062.4 2145.07
  5102.9 2147.88  5113.0 2147.49  5123.1 2145.93  5153.5 2144.28  5183.8 2145.46
  5209.2 2147.60  5234.4 2149.15  5285.0 2150.85  5527.6 2155.36  5532.7 2156.05
  5588.5 2157.73  5629.0 2159.78  5659.1 2160.34  5669.5 2161.33  5730.9 2163.23
#Mann=4,-1,0
  4738.2     0.1       0  5005.6    0.05       0  5018.5     0.1       0
  5209.2    0.07       0
Bank Sta=5005.6,5018.5
Exp/Cntr=0.3,0.1

Type RM Length L Ch R = 1,27172,199,199,199
BEGIN DESCRIPTION:
Flat Rock Creek 2 58.0
END DESCRIPTION:
XS GIS Cut Line= 3
      1789489.29     13918568.11      1789538.78     13918337.61
      1789668.98     13917710.03
#Sta/Elev= 30
  4751.2 2167.24  4801.3 2167.32  4826.0 2166.19  4850.7 2164.04  4895.0 2155.93
  4938.5 2150.51  4944.4 2149.02  4969.2 2145.14  4979.4 2144.15  4985.7 2142.51
  4990.0 2142.51  5003.1 2139.91  5003.6 2139.41  5016.5 2139.41  5017.0 2139.91
  5020.3 2141.08  5038.9 2142.12  5044.0 2141.94  5050.9 2143.03  5061.1 2143.58
  5112.2 2145.29  5122.4 2146.47  5139.2 2147.20  5183.0 2148.22  5377.7 2152.89
  5384.8 2153.54  5389.9 2153.31  5535.2 2157.81  5585.4 2160.57  5627.9 2162.10
#Mann=4,-1,0
  4751.2     0.1       0  5003.1    0.05       0  5017.0     0.1       0
  5183.0    0.07       0
Bank Sta=5003.1,5017
Exp/Cntr=0.3,0.1

Type RM Length L Ch R = 1,26973,485,485,485
BEGIN DESCRIPTION:
Flat Rock Creek 2 57.0
END DESCRIPTION:
XS GIS Cut Line= 3
      1789624.99     13918575.02      1789725.00     13918375.00
      1790075.02     13917774.96
#Sta/Elev= 30
  4776.8 2163.88  4821.5 2163.36  4829.9 2160.32  4835.5 2160.83  4857.9 2157.72
  4866.3 2157.72  4902.6 2152.28  4933.3 2149.77  4955.7 2145.80  4992.0 2141.38
  4997.6 2139.80  5008.3 2140.85  5016.6 2139.23  5017.1 2138.73  5030.5 2139.23
  5045.5 2141.91  5051.3 2141.59  5058.3 2143.18  5072.8 2144.09  5131.5 2144.99
  5148.4 2146.28  5205.9 2147.89  5220.4 2149.50  5227.4 2148.95  5323.3 2151.57
  5382.1 2154.79  5425.1 2155.59  5475.1 2158.04  5526.8 2158.94  5695.1 2167.96
#Mann=4,-1,0
  4776.8     0.1       0  5016.6    0.05       0  5030.5     0.1       0
  5148.4    0.07       0
Bank Sta=5016.6,5030.5
Exp/Cntr=0.3,0.1

Type RM Length L Ch R = 1,26488,466,466,466
BEGIN DESCRIPTION:
Flat Rock Creek 2 56.0
END DESCRIPTION:
XS GIS Cut Line= 3
      1789775.02     13918674.99      1790175.00     13918375.00
      1790774.97     13918175.01
#Sta/Elev= 30
  4498.5 2161.21  4572.1 2158.69  4620.4 2157.23  4641.2 2154.89  4670.4 2153.25
  4691.2 2150.55  4745.5 2146.82  4770.4 2146.19  4826.6 2142.14  4884.9 2141.46
  4891.2 2140.55  4920.4 2140.96  4977.9 2138.63  4978.4 2138.13  4991.9 2138.63
  4995.4 2139.67  5030.1 2142.78  5114.4 2142.76  5146.1 2145.97  5198.8 2148.61
  5262.0 2153.38  5314.7 2158.95  5318.1 2172.04  5325.2 2199.38  5335.8 2161.30
  5403.2 2166.66  5472.8 2170.49  5515.0 2175.40  5557.1 2178.84  5630.9 2188.16
#Mann=7,-1,0
  4498.5    0.07       0  4572.1     0.1       0  4745.5    0.07       0
  4977.9    0.05       0  4991.9    0.07       0  5318.1     0.1       0
  5403.2    0.07       0
Bank Sta=4977.9,4991.9
Exp/Cntr=0.3,0.1

Type RM Length L Ch R = 1,26022,482,482,482
BEGIN DESCRIPTION:
Flat Rock Creek 2 55.0
END DESCRIPTION:
XS GIS Cut Line= 3
      1790174.98     13918825.01      1790525.00     13918625.00
      1790725.01     13918575.00
#Sta/Elev= 30
  4592.2 2153.07  4659.2 2150.83  4702.4 2147.09  4724.0 2146.15  4730.4 2145.09
  4804.6 2140.61  4879.4 2141.30  4901.0 2143.82  4914.7 2144.57  4937.7 2144.23
  4965.8 2141.44  4972.3 2138.43  4981.7 2135.43  4987.4 2134.50  4997.9 2134.25
  4998.6 2132.66  4999.1 2132.16  5012.6 2132.66  5036.6 2137.36  5046.9 2142.87
  5054.6 2149.57  5067.5 2156.00  5077.8 2160.57  5095.8 2166.17  5101.0 2166.91
  5108.7 2169.52  5142.2 2175.87  5150.0 2178.51  5191.2 2188.41  5201.5 2189.31
#Mann=3,-1,0
  4592.2    0.07       0  4998.6    0.05       0  5012.6    0.07       0
Bank Sta=4998.6,5012.6
Exp/Cntr=0.3,0.1

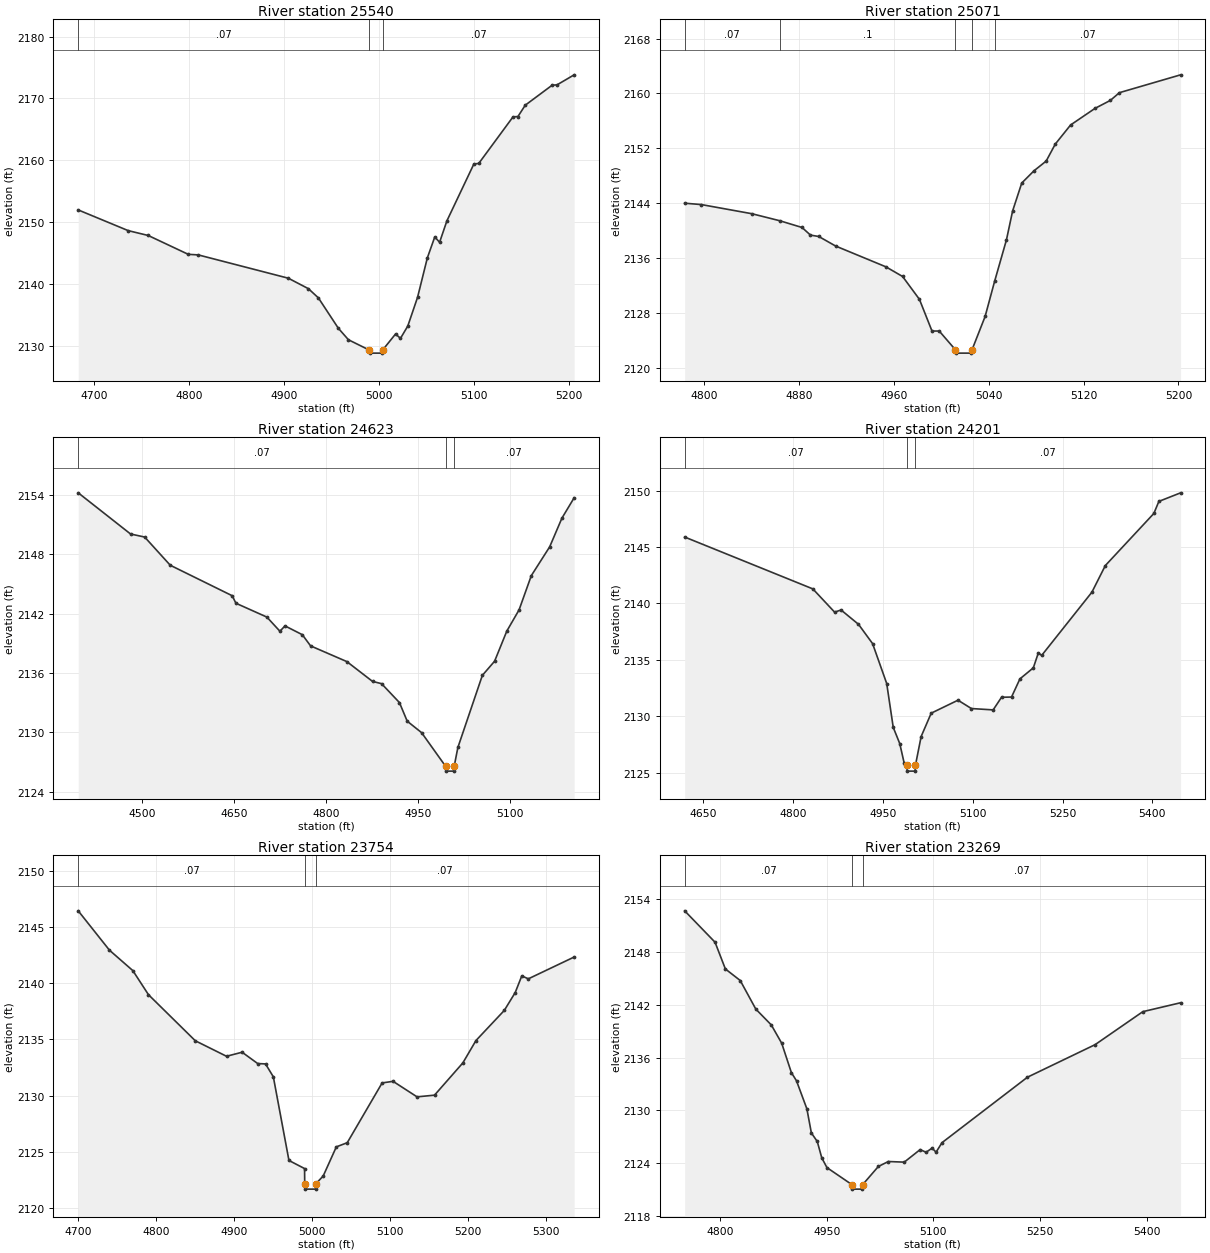
Type RM Length L Ch R = 1,25540,469,469,469
BEGIN DESCRIPTION:
Flat Rock Creek 2 54.0
END DESCRIPTION:
XS GIS Cut Line= 3
      1790225.04     13918975.01      1790525.00     13919075.00
      1790724.96     13919025.01
#Sta/Elev= 30
  4683.4 2151.98  4736.1 2148.63  4757.1 2147.85  4799.3 2144.80  4809.8 2144.71
  4904.7 2140.94  4925.8 2139.25  4936.3 2137.77  4957.4 2132.84  4968.0 2130.99
  4989.9 2129.33  4990.4 2128.83  5003.5 2128.83  5004.0 2129.33  5017.6 2131.92
  5022.8 2131.22  5030.5 2133.21  5040.8 2137.86  5051.1 2144.23  5058.9 2147.61
  5064.0 2146.75  5071.7 2150.22  5100.1 2159.41  5105.2 2159.49  5141.3 2167.02
  5146.5 2167.08  5154.2 2168.91  5182.5 2172.14  5187.7 2172.20  5205.7 2173.82
#Mann=3,-1,0
  4683.4    0.07       0  4989.9    0.05       0  5004.0    0.07       0
Bank Sta=4989.9,5004
Exp/Cntr=0.3,0.1

Type RM Length L Ch R = 1,25071,448,448,448
BEGIN DESCRIPTION:
Flat Rock Creek 2 53.0
END DESCRIPTION:
XS GIS Cut Line= 3
      1790175.00     13919325.00      1790325.00     13919475.00
      1790525.01     13919525.00
#Sta/Elev= 30
  4783.5 2144.01  4797.6 2143.81  4840.1 2142.48  4863.8 2141.45  4882.5 2140.47
  4889.6 2139.36  4896.6 2139.16  4910.8 2137.77  4953.2 2134.74  4967.3 2133.33
  4981.5 2130.00  4992.1 2125.38  4998.2 2125.38  5011.8 2122.66  5012.3 2122.16
  5025.4 2122.16  5025.9 2122.66  5036.9 2127.50  5044.9 2132.62  5054.9 2138.67
  5060.1 2142.88  5067.8 2146.95  5078.1 2148.73  5088.4 2150.15  5096.1 2152.63
  5109.0 2155.41  5129.6 2157.83  5142.5 2158.99  5150.2 2160.12  5201.8 2162.72
#Mann=5,-1,0
  4783.5    0.07       0  4863.8     0.1       0  5011.8    0.05       0
  5025.9     0.1       0  5044.9    0.07       0
Bank Sta=5011.8,5025.9
Exp/Cntr=0.3,0.1

Type RM Length L Ch R = 1,24623,422,422,422
BEGIN DESCRIPTION:
Flat Rock Creek 2 52.0
END DESCRIPTION:
XS GIS Cut Line= 3
      1789574.97     13919474.98      1790075.00     13919825.00
      1790275.04     13919825.00
#Sta/Elev= 30
  4395.0 2154.21  4480.5 2150.05  4503.6 2149.74  4545.4 2146.89  4646.6 2143.81
  4652.7 2143.05  4703.3 2141.65  4724.6 2140.22  4732.9 2140.76  4761.2 2139.87
  4774.7 2138.74  4834.0 2137.15  4875.9 2135.15  4890.7 2134.92  4919.9 2133.01
  4932.6 2131.13  4956.1 2129.97  4995.2 2126.58  4995.7 2126.08  5008.9 2126.08
  5009.4 2126.58  5015.4 2128.47  5055.4 2135.76  5075.4 2137.19  5095.4 2140.24
  5115.4 2142.38  5135.4 2145.84  5165.4 2148.75  5185.4 2151.65  5205.4 2153.71
#Mann=3,-1,0
  4395.0    0.07       0  4995.2    0.05       0  5009.4    0.07       0
Bank Sta=4995.2,5009.4
Exp/Cntr=0.3,0.1

Type RM Length L Ch R = 1,24201,447,447,447
BEGIN DESCRIPTION:
Flat Rock Creek 2 51.0
END DESCRIPTION:
XS GIS Cut Line= 3
      1789574.99     13919674.97      1789725.00     13920025.00
      1790124.97     13920224.98
#Sta/Elev= 30
  4619.2 2145.89  4833.2 2141.29  4869.5 2139.23  4880.3 2139.42  4909.4 2138.15
  4932.9 2136.44  4956.5 2132.90  4967.4 2129.01  4978.3 2127.57  4985.5 2125.88
  4990.2 2125.63  4990.7 2125.13  5003.9 2125.13  5004.4 2125.63  5014.0 2128.20
  5030.8 2130.27  5075.5 2131.42  5097.9 2130.68  5134.2 2130.56  5148.2 2131.68
  5164.9 2131.70  5178.9 2133.31  5201.3 2134.29  5209.7 2135.62  5215.2 2135.39
  5299.1 2141.00  5321.5 2143.36  5402.5 2147.98  5410.9 2149.05  5447.2 2149.81
#Mann=3,-1,0
  4619.2    0.07       0  4990.2    0.05       0  5004.4    0.07       0
Bank Sta=4990.2,5004.4
Exp/Cntr=0.3,0.1

Type RM Length L Ch R = 1,23754,485,485,485
BEGIN DESCRIPTION:
Flat Rock Creek 2 50.0
END DESCRIPTION:
XS GIS Cut Line= 3
      1789175.04     13920375.00      1789475.00     13920375.00
      1789775.03     13920525.02
#Sta/Elev= 30
  4700.2 2146.44  4740.2 2142.94  4770.2 2141.12  4790.2 2138.98  4850.2 2134.88
  4890.2 2133.50  4910.2 2133.86  4930.2 2132.85  4940.2 2132.82  4950.2 2131.67
  4970.2 2124.23  4990.2 2123.51  4990.4 2122.18  4990.9 2121.68  5004.5 2121.68
  5005.0 2122.18  5014.1 2122.85  5030.9 2125.44  5044.9 2125.81  5089.6 2131.13
  5103.6 2131.27  5134.3 2129.89  5156.7 2130.04  5193.0 2132.91  5209.8 2134.90
  5246.1 2137.58  5260.1 2139.17  5268.5 2140.65  5276.9 2140.39  5335.6 2142.33
#Mann=3,-1,0
  4700.2    0.07       0  4990.4    0.05       0  5005.0    0.07       0
Bank Sta=4990.4,5005
Exp/Cntr=0.3,0.1

Type RM Length L Ch R = 1,23269,467,467,467
BEGIN DESCRIPTION:
Flat Rock Creek 2 49.0
END DESCRIPTION:
XS GIS Cut Line= 3
      1789225.03     13921024.96      1789375.00     13920825.00
      1789775.03     13920624.99
#Sta/Elev= 30
  4750.3 2152.63  4793.0 2149.07  4807.5 2146.04  4828.4 2144.73  4850.3 2141.49
  4872.1 2139.69  4886.7 2137.62  4900.3 2134.29  4907.5 2133.36  4922.1 2130.18
  4928.4 2127.45  4936.7 2126.48  4943.0 2124.63  4950.3 2123.52  4985.6 2121.58
  4986.1 2121.08  4999.9 2121.08  5000.4 2121.58  5022.6 2123.65  5036.6 2124.21
  5059.0 2124.14  5081.3 2125.56  5089.7 2125.26  5098.1 2125.73  5103.7 2125.27
  5112.1 2126.35  5232.2 2133.77  5327.3 2137.46  5394.4 2141.20  5447.5 2142.21
#Mann=3,-1,0
  4750.3    0.07       0  4985.6    0.05       0  5000.4    0.07       0
Bank Sta=4985.6,5000.4
Exp/Cntr=0.3,0.1

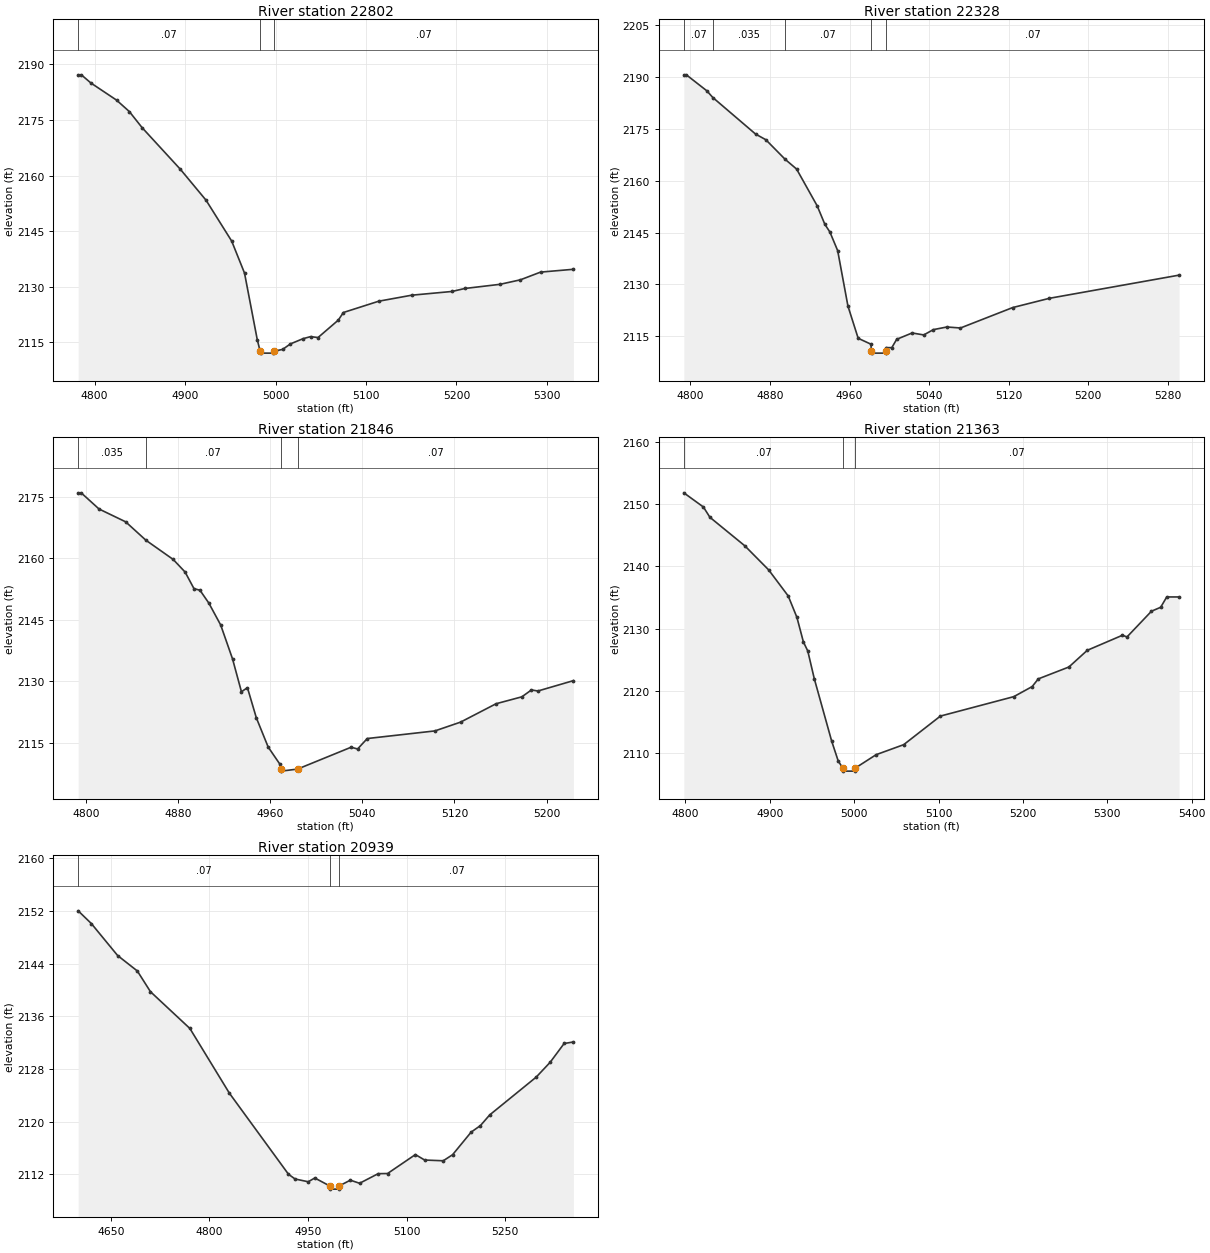
Type RM Length L Ch R = 1,22802,474,474,474
BEGIN DESCRIPTION:
Flat Rock Creek 2 48.0
END DESCRIPTION:
XS GIS Cut Line= 3
      1789425.00     13921375.00      1789575.00     13921225.00
      1789724.98     13920925.04
#Sta/Elev= 30
  4781.8 2187.17  4785.3 2187.17  4795.9 2184.96  4824.2 2180.35  4838.4 2177.25
  4852.5 2172.91  4894.9 2161.65  4923.2 2153.33  4951.5 2142.32  4965.7 2133.68
  4979.8 2115.71  4983.0 2112.58  4983.5 2112.08  4997.3 2112.08  4997.8 2112.58
  5007.9 2113.09  5016.3 2114.55  5030.3 2115.97  5038.7 2116.53  5047.0 2116.29
  5069.4 2120.99  5075.0 2123.04  5114.1 2126.09  5150.5 2127.71  5195.2 2128.72
  5209.2 2129.52  5248.3 2130.65  5270.7 2131.86  5293.0 2133.94  5329.3 2134.70
#Mann=3,-1,0
  4781.8    0.07       0  4983.0    0.05       0  4997.8    0.07       0
Bank Sta=4983,4997.8
Exp/Cntr=0.3,0.1

Type RM Length L Ch R = 1,22328,482,482,482
BEGIN DESCRIPTION:
Flat Rock Creek 2 47.0
END DESCRIPTION:
XS GIS Cut Line= 3
      1789925.01     13921624.96      1789975.00     13921425.00
      1790125.02     13921174.97
#Sta/Elev= 30
  4793.5 2190.70  4796.0 2190.70  4816.6 2186.07  4822.6 2184.13  4865.6 2173.54
  4875.9 2171.90  4895.3 2166.23  4906.8 2163.41  4927.5 2152.75  4935.2 2147.41
  4940.3 2145.16  4948.1 2139.77  4958.4 2123.74  4968.7 2114.39  4981.6 2112.67
  4981.9 2110.59  4982.4 2110.09  4996.2 2110.09  4996.7 2110.59  4997.0 2111.68
  5002.5 2111.68  5007.4 2114.09  5022.9 2115.93  5034.6 2115.36  5044.3 2116.90
  5057.9 2117.66  5071.5 2117.37  5124.0 2123.29  5160.9 2125.97  5291.2 2132.68
#Mann=5,-1,0
  4793.5    0.07       0  4822.6   0.035       0  4895.3    0.07       0
  4981.9    0.05       0  4996.7    0.07       0
Bank Sta=4981.9,4996.7
Exp/Cntr=0.3,0.1

Type RM Length L Ch R = 1,21846,483,483,483
BEGIN DESCRIPTION:
Flat Rock Creek 2 46.0
END DESCRIPTION:
XS GIS Cut Line= 3
      1790375.00     13921625.01      1790425.00     13921425.00
      1790324.99     13921224.98
#Sta/Elev= 30
  4793.4 2176.00  4796.0 2176.00  4811.5 2172.05  4834.6 2168.92  4852.2 2164.42
  4875.9 2159.72  4886.2 2156.65  4893.9 2152.60  4899.1 2152.21  4906.8 2149.07
  4917.1 2143.71  4927.4 2135.41  4935.1 2127.41  4940.3 2128.41  4948.0 2121.07
  4958.3 2113.91  4968.6 2109.67  4969.0 2108.53  4969.5 2108.03  4983.8 2108.53
  5030.3 2113.87  5035.9 2113.44  5044.3 2115.99  5103.0 2117.85  5125.3 2120.00
  5156.1 2124.49  5178.5 2126.18  5186.8 2127.86  5192.4 2127.60  5223.2 2130.13
#Mann=4,-1,0
  4793.4   0.035       0  4852.2    0.07       0  4969.0    0.05       0
  4983.8    0.07       0
Bank Sta=4969,4983.8
Exp/Cntr=0.3,0.1

Type RM Length L Ch R = 1,21363,424,424,424
BEGIN DESCRIPTION:
Flat Rock Creek 2 45.0
END DESCRIPTION:
XS GIS Cut Line= 3
      1790925.00     13921525.01      1790875.00     13921325.00
      1790724.98     13920974.96
#Sta/Elev= 30
  4798.1 2151.79  4821.3 2149.51  4829.0 2147.86  4870.3 2143.29  4898.6 2139.42
  4921.8 2135.23  4932.1 2131.80  4939.8 2127.85  4945.0 2126.39  4952.7 2121.95
  4973.3 2111.93  4981.1 2108.72  4986.5 2107.60  4987.0 2107.10  5000.9 2107.10
  5001.4 2107.60  5026.0 2109.74  5058.7 2111.35  5102.2 2115.94  5189.2 2119.06
  5211.0 2120.68  5218.2 2121.91  5254.5 2123.82  5276.3 2126.50  5318.0 2128.92
  5323.4 2128.65  5352.4 2132.78  5363.3 2133.41  5370.5 2135.07  5385.1 2135.07
#Mann=3,-1,0
  4798.1    0.07       0  4986.5    0.05       0  5001.4    0.07       0
Bank Sta=4986.5,5001.4
Exp/Cntr=0.3,0.1

Type RM Length L Ch R = 1,20939,449,449,449
BEGIN DESCRIPTION:
Flat Rock Creek 2 44.0
END DESCRIPTION:
XS GIS Cut Line= 3
      1791225.00     13921524.96      1791225.00     13921125.00
      1790975.01     13920875.01
#Sta/Elev= 30
  4600.4 2152.03  4620.4 2150.10  4660.4 2145.24  4690.4 2142.89  4710.4 2139.74
  4770.4 2134.15  4830.4 2124.33  4920.4 2112.00  4930.4 2111.28  4950.4 2110.86
  4960.4 2111.43  4982.9 2110.24  4983.4 2109.74  4997.3 2109.74  4997.8 2110.24
  5014.5 2111.10  5028.6 2110.63  5056.9 2112.09  5071.1 2112.11  5113.5 2114.99
  5127.6 2114.16  5155.9 2114.05  5170.1 2114.97  5198.3 2118.40  5212.5 2119.40
  5226.6 2121.02  5297.3 2126.76  5318.6 2129.02  5339.8 2131.87  5353.9 2132.10
#Mann=3,-1,0
  4600.4    0.07       0  4982.9    0.05       0  4997.8    0.07       0
Bank Sta=4982.9,4997.8
Exp/Cntr=0.3,0.1