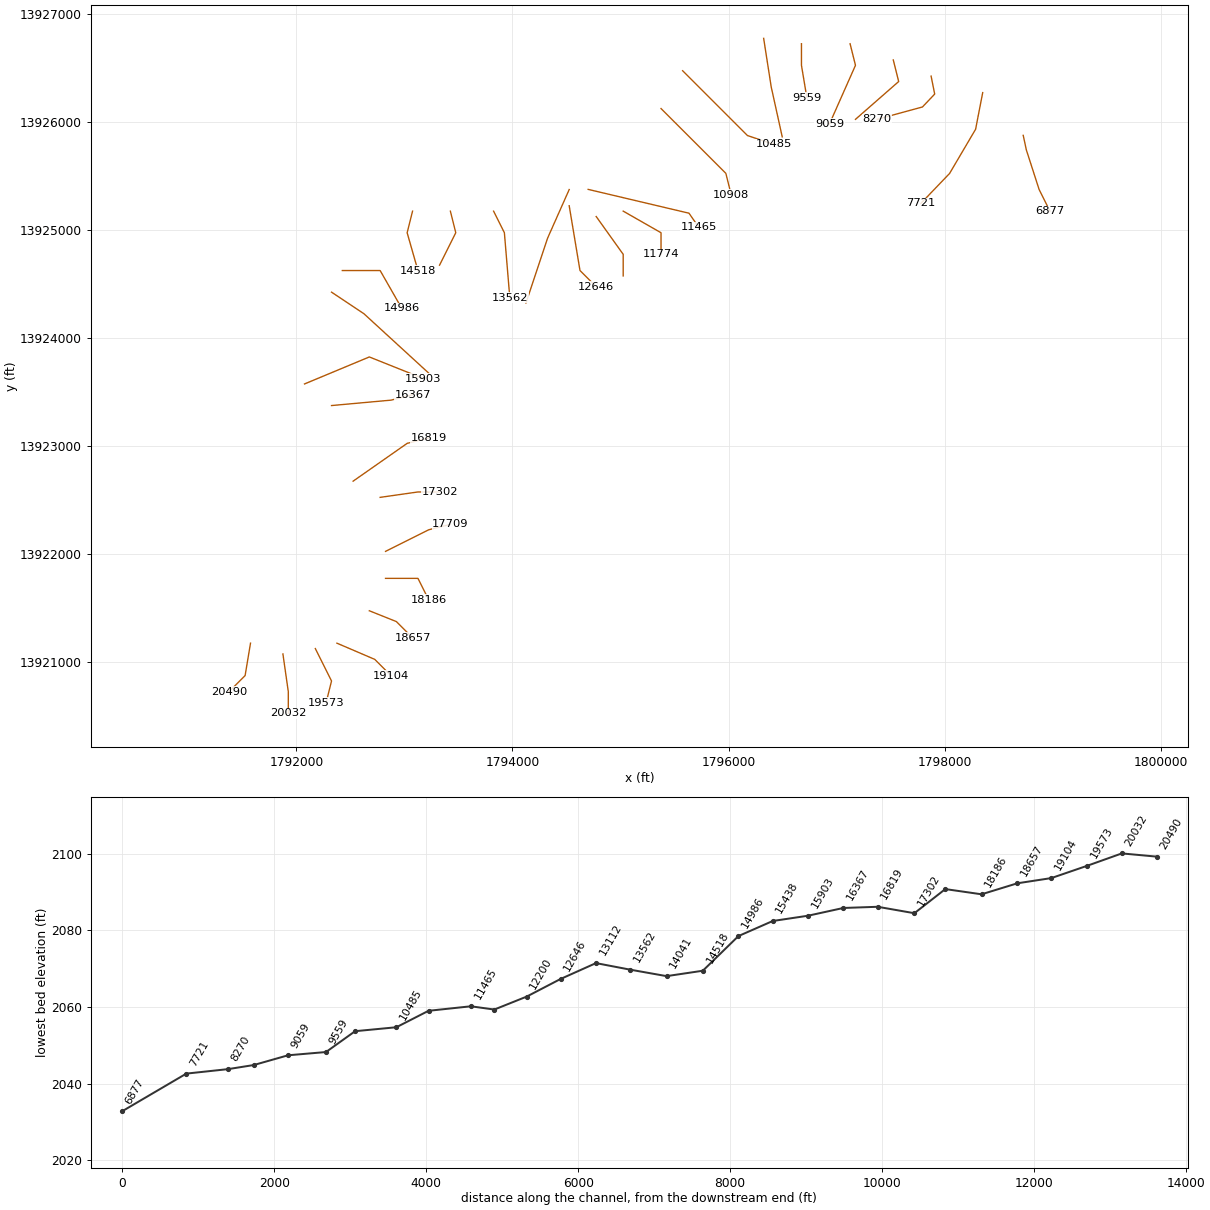
HEC-RAS study Flat Rock Creek 2.prj: Flat Rock Creek 2 Base Level Engineering

--- Flat Rock Creek 2.g01 (geometry) --- (continued)

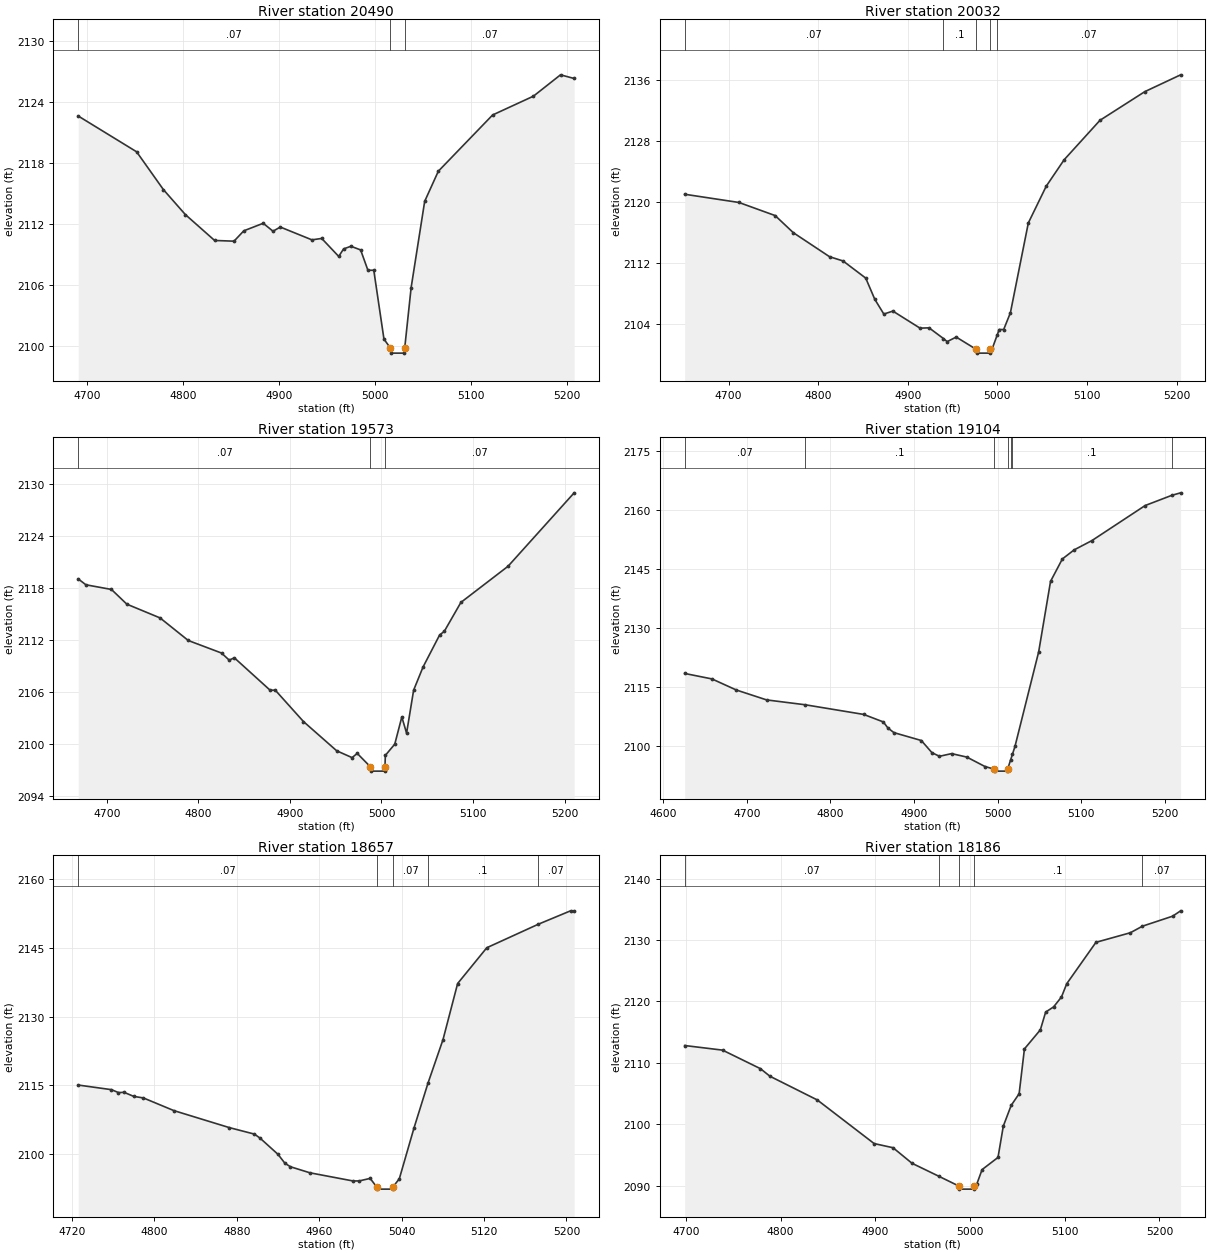
Type RM Length L Ch R = 1,20490,458,458,458
BEGIN DESCRIPTION:
Flat Rock Creek 2 43.0
END DESCRIPTION:
XS GIS Cut Line= 3
      1791575.00     13921175.02      1791525.00     13920875.00
      1791374.99     13920724.99
#Sta/Elev= 30
  4691.1 2122.59  4751.9 2119.07  4779.8 2115.35  4802.6 2112.90  4833.1 2110.35
  4853.3 2110.28  4863.5 2111.30  4883.7 2112.04  4893.9 2111.26  4901.5 2111.67
  4934.4 2110.41  4944.6 2110.55  4962.3 2108.78  4967.4 2109.52  4975.0 2109.78
  4985.1 2109.42  4992.7 2107.42  4998.8 2107.42  5009.4 2100.65  5016.1 2099.77
  5016.6 2099.27  5030.5 2099.27  5031.0 2099.77  5037.7 2105.72  5051.8 2114.20
  5066.0 2117.16  5122.5 2122.69  5165.0 2124.54  5193.2 2126.64  5207.4 2126.28
#Mann=3,-1,0
  4691.1    0.07       0  5016.1    0.05       0  5031.0    0.07       0
Bank Sta=5016.1,5031
Exp/Cntr=0.3,0.1

Type RM Length L Ch R = 1,20032,459,459,459
BEGIN DESCRIPTION:
Flat Rock Creek 2 42.0
END DESCRIPTION:
XS GIS Cut Line= 3
      1791875.00     13921075.03      1791925.00     13920725.00
      1791925.00     13920524.98
#Sta/Elev= 30
  4650.9 2120.97  4711.5 2119.89  4751.9 2118.17  4772.1 2115.93  4812.6 2112.77
  4827.7 2112.21  4853.0 2109.96  4863.1 2107.18  4873.2 2105.24  4883.3 2105.63
  4913.6 2103.39  4923.7 2103.43  4939.8 2102.02  4943.9 2101.62  4954.0 2102.22
  4976.3 2100.61  4976.8 2100.11  4991.7 2100.11  4992.2 2100.61  4994.4 2100.76
  4999.7 2102.47  5002.0 2103.21  5007.0 2103.21  5014.5 2105.41  5034.5 2117.20
  5054.5 2122.03  5074.5 2125.50  5114.5 2130.68  5164.5 2134.44  5204.5 2136.65
#Mann=5,-1,0
  4650.9    0.07       0  4939.8     0.1       0  4976.3    0.05       0
  4992.2     0.1       0  4999.7    0.07       0
Bank Sta=4976.3,4992.2
Exp/Cntr=0.3,0.1

Type RM Length L Ch R = 1,19573,469,469,469
BEGIN DESCRIPTION:
Flat Rock Creek 2 41.0
END DESCRIPTION:
XS GIS Cut Line= 3
      1792175.00     13921124.99      1792325.00     13920825.00
      1792274.99     13920624.96
#Sta/Elev= 30
  4668.8 2119.08  4677.2 2118.40  4705.1 2117.86  4721.9 2116.16  4758.2 2114.57
  4789.0 2111.96  4825.3 2110.51  4833.7 2109.69  4839.3 2109.96  4878.4 2106.21
  4884.0 2106.22  4914.8 2102.59  4951.1 2099.21  4967.9 2098.42  4973.5 2098.91
  4987.9 2097.36  4988.4 2096.86  5003.3 2096.86  5003.8 2097.36  5004.2 2098.68
  5014.5 2099.98  5022.2 2103.12  5027.4 2101.25  5035.1 2106.22  5045.4 2108.90
  5063.5 2112.60  5068.6 2113.02  5086.7 2116.36  5138.2 2120.54  5210.4 2129.03
#Mann=3,-1,0
  4668.8    0.07       0  4987.9    0.05       0  5003.8    0.07       0
Bank Sta=4987.9,5003.8
Exp/Cntr=0.3,0.1

Type RM Length L Ch R = 1,19104,447,447,447
BEGIN DESCRIPTION:
Flat Rock Creek 2 40.0
END DESCRIPTION:
XS GIS Cut Line= 3
      1792375.00     13921175.00      1792725.00     13921025.00
      1792874.99     13920875.01
#Sta/Elev= 30
  4625.7 2118.49  4658.3 2117.10  4687.4 2114.29  4723.6 2111.77  4769.9 2110.53
  4839.7 2108.08  4863.2 2106.17  4868.7 2104.62  4875.9 2103.45  4908.6 2101.45
  4921.3 2098.36  4930.3 2097.44  4944.8 2098.12  4963.0 2097.24  4984.7 2094.84
  4995.8 2094.17  4996.3 2093.67  5011.3 2093.67  5011.8 2094.17  5015.5 2096.61
  5017.6 2097.99  5020.6 2099.97  5048.9 2123.98  5063.1 2141.89  5077.2 2147.58
  5091.3 2149.89  5112.6 2152.26  5176.2 2161.16  5208.0 2163.75  5218.6 2164.39
#Mann=7,-1,0
  4625.7    0.07       0  4769.9     0.1       0  4995.8    0.05       0
  5011.8     0.1       0  5015.5    0.07       0  5017.6     0.1       0
  5208.0    0.07       0
Bank Sta=4995.8,5011.8
Exp/Cntr=0.3,0.1

Type RM Length L Ch R = 1,18657,471,471,471
BEGIN DESCRIPTION:
Flat Rock Creek 2 39.0
END DESCRIPTION:
XS GIS Cut Line= 3
      1792674.97     13921475.01      1792925.00     13921375.00
      1793074.98     13921225.02
#Sta/Elev= 30
  4726.1 2115.06  4758.4 2114.05  4765.2 2113.41  4770.6 2113.47  4780.0 2112.58
  4789.4 2112.24  4819.0 2109.47  4872.9 2105.75  4897.1 2104.34  4902.5 2103.48
  4920.0 2099.92  4926.7 2097.98  4932.1 2097.20  4951.0 2095.88  4992.7 2094.10
  4998.9 2094.10  5009.5 2094.66  5015.7 2092.81  5016.2 2092.31  5031.2 2092.31
  5031.7 2092.81  5037.8 2094.58  5052.0 2105.64  5065.7 2115.53  5080.2 2124.99
  5094.4 2137.25  5122.7 2145.07  5172.5 2150.19  5204.0 2153.14  5207.5 2153.14
#Mann=5,-1,0
  4726.1    0.07       0  5015.7    0.05       0  5031.7    0.07       0
  5065.7     0.1       0  5172.5    0.07       0
Bank Sta=5015.7,5031.7
Exp/Cntr=0.3,0.1

Type RM Length L Ch R = 1,18186,477,477,477
BEGIN DESCRIPTION:
Flat Rock Creek 2 38.0
END DESCRIPTION:
XS GIS Cut Line= 3
      1792824.99     13921775.00      1793125.00     13921775.00
      1793224.99     13921575.02
#Sta/Elev= 30
  4698.8 2112.82  4738.8 2112.07  4778.8 2109.05  4788.8 2107.82  4838.8 2103.96
  4898.8 2096.86  4918.8 2096.18  4938.8 2093.65  4966.8 2091.56  4988.3 2089.94
  4988.8 2089.44  5003.8 2089.44  5004.3 2089.94  5007.2 2090.26  5012.8 2092.62
  5029.6 2094.60  5035.2 2099.70  5043.5 2103.07  5051.9 2104.97  5057.5 2112.27
  5074.3 2115.37  5079.9 2118.26  5088.3 2119.11  5096.6 2120.72  5102.2 2122.89
  5133.0 2129.62  5169.3 2131.18  5182.1 2132.25  5214.0 2133.88  5222.4 2134.75
#Mann=5,-1,0
  4698.8    0.07       0  4966.8     0.1       0  4988.3    0.05       0
  5004.3     0.1       0  5182.1    0.07       0
Bank Sta=4988.3,5004.3
Exp/Cntr=0.3,0.1

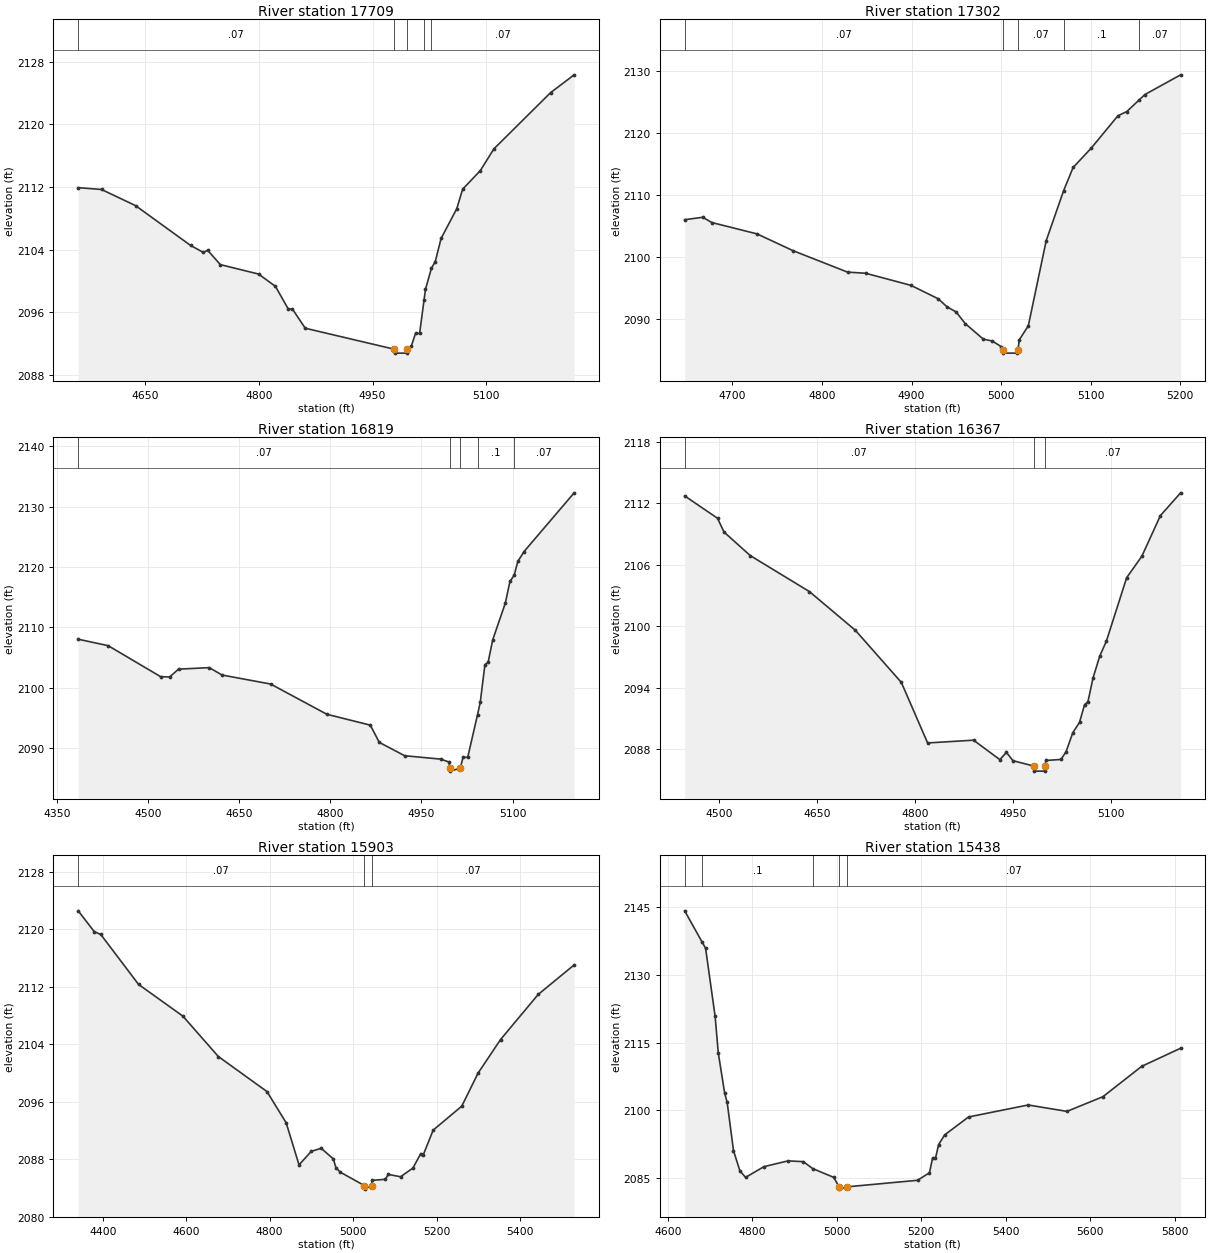
Type RM Length L Ch R = 1,17709,407,407,407
BEGIN DESCRIPTION:
Flat Rock Creek 2 37.0
END DESCRIPTION:
XS GIS Cut Line= 3
      1792825.01     13922025.00      1793225.00     13922225.00
      1793425.04     13922275.01
#Sta/Elev= 30
  4562.2 2111.93  4592.9 2111.70  4637.7 2109.64  4710.3 2104.55  4727.1 2103.66
  4732.7 2103.94  4749.5 2102.10  4799.8 2100.90  4822.1 2099.32  4838.9 2096.44
  4844.5 2096.42  4861.3 2093.98  4978.6 2091.30  4979.1 2090.80  4994.9 2090.80
  4995.4 2091.30  5001.0 2091.67  5006.6 2093.32  5012.0 2093.32  5017.8 2097.55
  5019.7 2098.94  5027.6 2101.65  5032.6 2102.49  5040.3 2105.45  5060.9 2109.23
  5068.7 2111.74  5091.9 2114.10  5109.9 2116.89  5184.6 2124.07  5215.6 2126.34
#Mann=5,-1,0
  4562.2    0.07       0  4978.6    0.05       0  4995.4    0.07       0
  5017.8     0.1       0  5027.6    0.07       0
Bank Sta=4978.6,4995.4
Exp/Cntr=0.3,0.1

Type RM Length L Ch R = 1,17302,483,483,483
BEGIN DESCRIPTION:
Flat Rock Creek 2 36.0
END DESCRIPTION:
XS GIS Cut Line= 3
      1792775.05     13922525.01      1793125.00     13922575.00
      1793325.00     13922575.00
#Sta/Elev= 30
  4646.8 2106.00  4667.0 2106.39  4677.1 2105.54  4727.6 2103.71  4768.0 2100.99
  4828.6 2097.55  4848.8 2097.37  4899.3 2095.42  4929.6 2093.27  4939.7 2091.95
  4949.8 2091.13  4959.9 2089.26  4980.1 2086.75  4990.2 2086.45  5000.3 2085.52
  5001.9 2085.00  5002.4 2084.50  5018.2 2084.50  5018.7 2085.00  5020.3 2086.66
  5030.3 2088.89  5050.3 2102.63  5069.8 2110.70  5080.3 2114.41  5100.3 2117.49
  5130.3 2122.74  5140.3 2123.43  5153.7 2125.25  5160.3 2126.15  5200.3 2129.34
#Mann=5,-1,0
  4646.8    0.07       0  5001.9    0.05       0  5018.7    0.07       0
  5069.8     0.1       0  5153.7    0.07       0
Bank Sta=5001.9,5018.7
Exp/Cntr=0.3,0.1

Type RM Length L Ch R = 1,16819,452,452,452
BEGIN DESCRIPTION:
Flat Rock Creek 2 35.0
END DESCRIPTION:
XS GIS Cut Line= 3
      1792524.99     13922674.99      1793025.00     13923025.00
      1793225.01     13923075.00
#Sta/Elev= 30
  4385.0 2108.04  4434.3 2106.97  4520.6 2101.84  4535.4 2101.78  4550.2 2103.08
  4600.8 2103.33  4621.7 2102.11  4701.9 2100.61  4794.4 2095.60  4865.9 2093.80
  4880.7 2090.94  4922.5 2088.73  4981.8 2088.17  4995.3 2087.69  4997.2 2086.68
  4997.7 2086.18  5014.1 2086.68  5018.5 2088.46  5026.3 2088.48  5042.5 2095.56
  5046.9 2097.58  5054.6 2103.82  5059.8 2104.20  5067.5 2107.96  5088.1 2114.00
  5095.8 2117.61  5102.8 2118.65  5108.7 2120.92  5119.0 2122.57  5201.5 2132.30
#Mann=5,-1,0
  4385.0    0.07       0  4997.2    0.05       0  5014.1    0.07       0
  5042.5     0.1       0  5102.8    0.07       0
Bank Sta=4997.2,5014.1
Exp/Cntr=0.3,0.1

Type RM Length L Ch R = 1,16367,464,464,464
BEGIN DESCRIPTION:
Flat Rock Creek 2 34.0
END DESCRIPTION:
XS GIS Cut Line= 3
      1792325.02     13923375.00      1792875.00     13923425.00
      1793075.00     13923475.00
#Sta/Elev= 30
  4447.7 2112.73  4497.9 2110.55  4507.9 2109.20  4548.1 2106.90  4638.5 2103.39
  4708.8 2099.61  4779.0 2094.53  4819.2 2088.62  4889.5 2088.89  4929.7 2086.99
  4939.7 2087.70  4949.7 2086.89  4981.2 2086.37  4981.7 2085.87  4998.1 2085.87
  4998.6 2086.37  4999.9 2086.91  5023.1 2087.01  5030.9 2087.76  5041.2 2089.62
  5051.5 2090.63  5059.2 2092.35  5064.4 2092.65  5072.1 2094.95  5082.4 2097.09
  5092.7 2098.58  5123.6 2104.75  5146.8 2106.84  5175.2 2110.81  5206.1 2113.03
#Mann=3,-1,0
  4447.7    0.07       0  4981.2    0.05       0  4998.6    0.07       0
Bank Sta=4981.2,4998.6
Exp/Cntr=0.3,0.1

Type RM Length L Ch R = 1,15903,465,465,465
BEGIN DESCRIPTION:
Flat Rock Creek 2 33.0
END DESCRIPTION:
XS GIS Cut Line= 3
      1792075.02     13923575.01      1792675.00     13923825.00
      1793175.00     13923625.00
#Sta/Elev= 30
  4341.3 2122.55  4379.7 2119.66  4395.4 2119.26  4485.9 2112.32  4592.1 2107.91
  4677.1 2102.29  4793.6 2097.42  4839.6 2093.08  4870.5 2087.22  4899.7 2089.10
  4923.6 2089.53  4952.8 2088.05  4958.8 2086.84  4969.6 2086.20  5026.9 2084.35
  5027.4 2083.85  5044.5 2084.35  5045.1 2085.06  5077.4 2085.22  5084.2 2085.90
  5113.8 2085.57  5143.4 2086.78  5162.3 2088.80  5167.6 2088.53  5191.9 2092.05
  5260.5 2095.39  5299.6 2099.99  5353.4 2104.65  5443.6 2110.92  5529.8 2115.03
#Mann=3,-1,0
  4341.3    0.07       0  5026.9    0.05       0  5044.5    0.07       0
Bank Sta=5026.9,5044.5
Exp/Cntr=0.3,0.1

Type RM Length L Ch R = 1,15438,452,452,452
BEGIN DESCRIPTION:
Flat Rock Creek 2 32.0
END DESCRIPTION:
XS GIS Cut Line= 3
      1792325.04     13924424.97      1792625.00     13924225.00
      1793224.96     13923675.03
#Sta/Elev= 30
  4639.6 2144.25  4680.5 2137.38  4689.1 2135.95  4711.7 2120.82  4719.2 2112.68
  4734.2 2103.83  4740.2 2101.73  4755.2 2091.02  4770.3 2086.54  4783.8 2085.08
  4827.3 2087.46  4884.4 2088.74  4920.5 2088.57  4942.8 2087.03  4992.6 2085.08
  5005.2 2082.97  5005.7 2082.47  5022.8 2082.97  5191.0 2084.43  5219.3 2086.11
  5226.7 2089.39  5233.5 2089.32  5240.9 2092.34  5255.1 2094.50  5311.8 2098.49
  5453.0 2101.15  5544.9 2099.73  5630.0 2102.99  5721.9 2109.73  5814.0 2113.75
#Mann=5,-1,0
  4639.6    0.07       0  4680.5     0.1       0  4942.8    0.07       0
  5005.2    0.05       0  5022.8    0.07       0
Bank Sta=5005.2,5022.8
Exp/Cntr=0.3,0.1

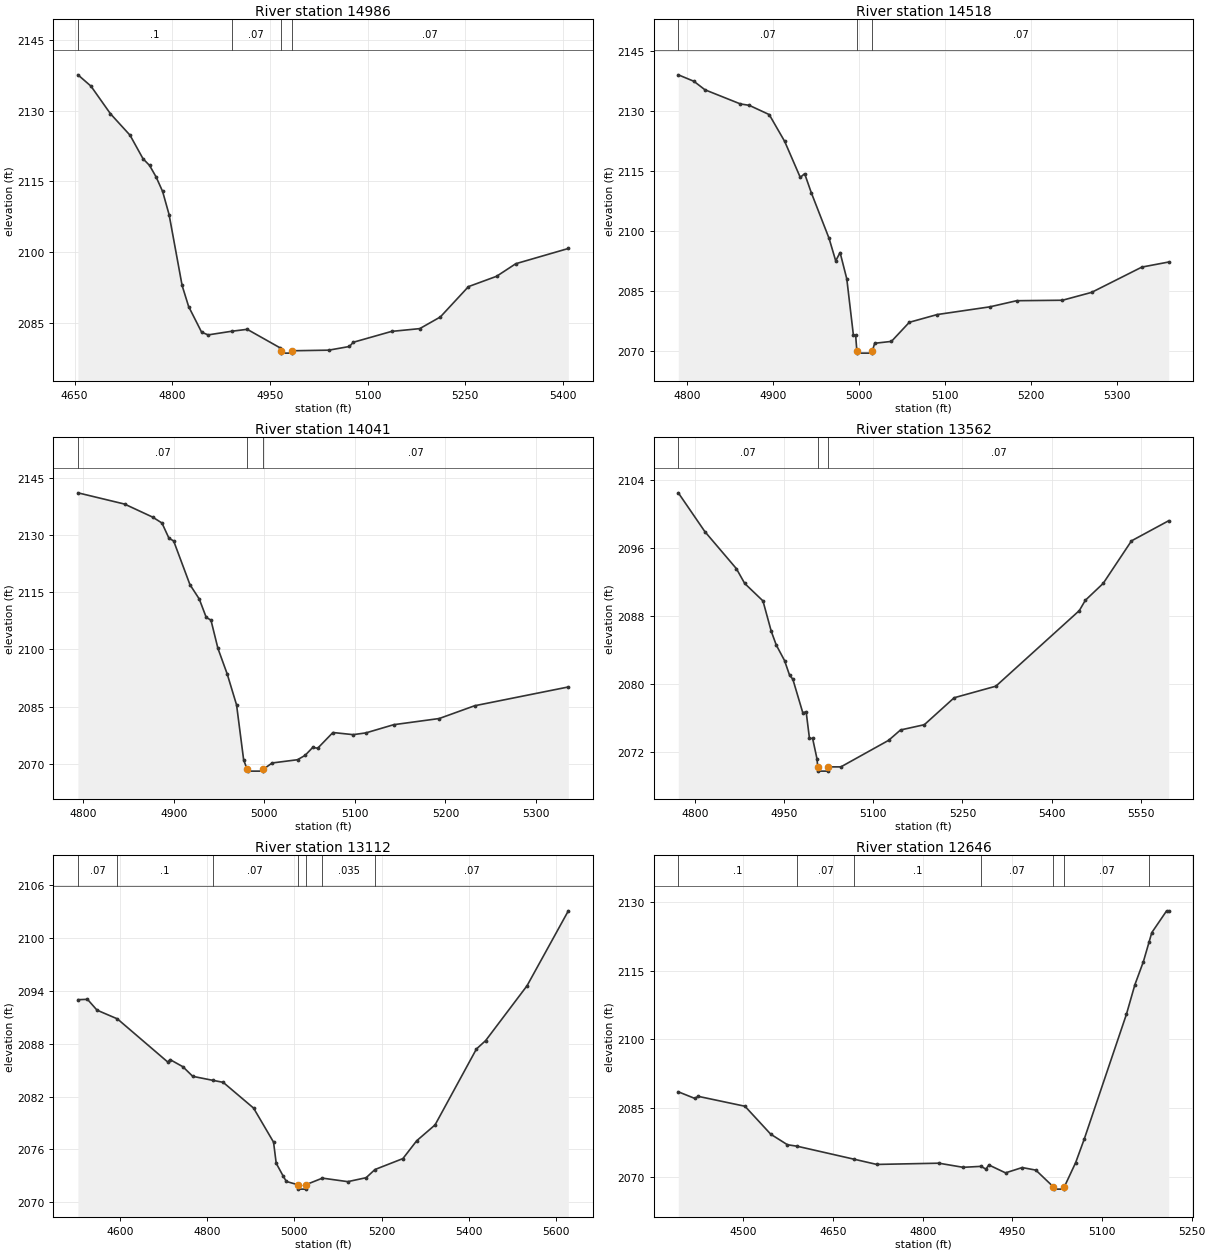
Type RM Length L Ch R = 1,14986,468,468,468
BEGIN DESCRIPTION:
Flat Rock Creek 2 31.0
END DESCRIPTION:
XS GIS Cut Line= 3
      1792424.95     13924625.00      1792775.00     13924625.00
      1792975.02     13924274.96
#Sta/Elev= 30
  4655.0 2137.57  4675.0 2135.17  4705.0 2129.30  4735.0 2124.76  4755.0 2119.76
  4765.0 2118.35  4775.0 2115.92  4785.0 2112.85  4795.0 2107.92  4815.0 2092.88
  4825.0 2088.42  4845.0 2082.96  4855.0 2082.40  4891.1 2083.17  4915.0 2083.58
  4965.0 2079.69  4966.2 2079.03  4966.7 2078.53  4983.3 2078.53  4983.8 2079.03
  5040.3 2079.16  5072.0 2079.94  5077.8 2080.83  5136.8 2083.14  5180.0 2083.73
  5211.6 2086.20  5254.8 2092.64  5298.0 2094.83  5327.5 2097.50  5408.2 2100.73
#Mann=4,-1,0
  4655.0     0.1       0  4891.1    0.07       0  4966.2    0.05       0
  4983.8    0.07       0
Bank Sta=4966.2,4983.8
Exp/Cntr=0.3,0.1

Type RM Length L Ch R = 1,14518,477,477,477
BEGIN DESCRIPTION:
Flat Rock Creek 2 30.0
END DESCRIPTION:
XS GIS Cut Line= 3
      1793075.01     13925175.03      1793025.00     13924975.00
      1793125.00     13924624.99
#Sta/Elev= 30
  4789.7 2139.00  4807.8 2137.39  4820.7 2135.26  4861.9 2131.73  4872.2 2131.38
  4895.4 2129.07  4913.4 2122.36  4931.5 2113.38  4936.6 2114.31  4944.3 2109.57
  4965.0 2098.15  4972.7 2092.54  4977.8 2094.61  4985.6 2088.03  4993.3 2073.94
  4995.9 2073.94  4997.3 2069.99  4997.8 2069.49  5014.8 2069.49  5015.3 2069.99
  5018.0 2071.95  5037.5 2072.42  5058.3 2077.19  5090.8 2079.13  5151.9 2081.05
  5183.1 2082.58  5236.4 2082.70  5270.2 2084.66  5328.7 2090.98  5359.9 2092.25
#Mann=3,-1,0
  4789.7    0.07       0  4997.3    0.05       0  5015.3    0.07       0
Bank Sta=4997.3,5015.3
Exp/Cntr=0.3,0.1

Type RM Length L Ch R = 1,14041,479,479,479
BEGIN DESCRIPTION:
Flat Rock Creek 2 29.0
END DESCRIPTION:
XS GIS Cut Line= 3
      1793425.00     13925175.00      1793475.00     13924975.00
      1793324.98     13924674.97
#Sta/Elev= 30
  4794.2 2141.09  4845.7 2138.14  4876.7 2134.72  4887.0 2133.17  4894.7 2129.19
  4899.9 2128.47  4917.9 2117.00  4928.2 2113.23  4935.9 2108.40  4941.1 2107.70
  4948.8 2100.29  4959.1 2093.53  4969.4 2085.44  4977.2 2071.05  4981.0 2068.58
  4981.5 2068.08  4998.5 2068.08  4999.0 2068.58  5008.7 2070.22  5036.7 2071.07
  5045.1 2072.22  5053.5 2074.30  5059.0 2074.09  5075.8 2078.21  5098.2 2077.65
  5112.2 2078.11  5142.9 2080.26  5193.2 2081.88  5232.3 2085.23  5335.8 2090.16
#Mann=3,-1,0
  4794.2    0.07       0  4981.0    0.05       0  4999.0    0.07       0
Bank Sta=4981,4999
Exp/Cntr=0.3,0.1

Type RM Length L Ch R = 1,13562,450,450,450
BEGIN DESCRIPTION:
Flat Rock Creek 2 28.0
END DESCRIPTION:
XS GIS Cut Line= 3
      1793825.02     13925174.96      1793925.00     13924975.00
      1793975.00     13924375.04
#Sta/Elev= 30
  4771.7 2102.50  4816.4 2097.94  4869.5 2093.58  4883.5 2091.84  4914.2 2089.79
  4928.2 2086.21  4936.6 2084.60  4950.5 2082.78  4958.9 2081.07  4964.5 2080.58
  4981.3 2076.63  4986.9 2076.76  4992.5 2073.62  4997.8 2073.62  5005.3 2071.17
  5006.3 2070.27  5006.8 2069.77  5023.9 2069.77  5024.4 2070.27  5045.4 2070.27
  5125.7 2073.39  5145.8 2074.61  5185.9 2075.23  5236.1 2078.40  5306.3 2079.76
  5446.8 2088.65  5456.9 2089.86  5487.0 2091.85  5534.6 2096.85  5597.3 2099.22
#Mann=3,-1,0
  4771.7    0.07       0  5006.3    0.05       0  5024.4    0.07       0
Bank Sta=5006.3,5024.4
Exp/Cntr=0.3,0.1

Type RM Length L Ch R = 1,13112,466,466,466
BEGIN DESCRIPTION:
Flat Rock Creek 2 27.0
END DESCRIPTION:
XS GIS Cut Line= 3
      1794525.01     13925375.02      1794325.00     13924925.00
      1794125.01     13924325.02
#Sta/Elev= 30
  4503.5 2093.01  4525.4 2093.05  4547.3 2091.82  4594.0 2090.83  4709.4 2085.93
  4714.9 2086.20  4744.3 2085.39  4766.8 2084.30  4812.3 2083.85  4836.6 2083.62
  4906.4 2080.69  4952.2 2076.82  4958.3 2074.42  4974.1 2072.98  4981.6 2072.35
  5007.9 2071.98  5008.4 2071.48  5025.7 2071.48  5026.2 2071.98  5064.3 2072.73
  5122.5 2072.33  5164.6 2072.78  5184.9 2073.71  5248.9 2074.95  5280.6 2076.98
  5322.7 2078.78  5417.6 2087.41  5438.7 2088.36  5533.6 2094.59  5628.4 2103.11
#Mann=7,-1,0
  4503.5    0.07       0  4594.0     0.1       0  4812.3    0.07       0
  5007.9    0.05       0  5026.2    0.07       0  5064.3   0.035       0
  5184.9    0.07       0
Bank Sta=5007.9,5026.2
Exp/Cntr=0.3,0.1

Type RM Length L Ch R = 1,12646,446,446,446
BEGIN DESCRIPTION:
Flat Rock Creek 2 26.0
END DESCRIPTION:
XS GIS Cut Line= 3
      1794525.00     13925225.00      1794625.00     13924625.00
      1794774.99     13924475.01
#Sta/Elev= 30
  4391.1 2088.58  4419.0 2087.12  4424.0 2087.60  4502.6 2085.43  4545.7 2079.33
  4573.6 2077.03  4589.7 2076.71  4685.8 2073.85  4723.1 2072.73  4827.0 2073.00
  4867.6 2072.10  4897.6 2072.31  4905.6 2071.71  4910.7 2072.61  4938.5 2070.89
  4966.4 2072.05  4989.2 2071.49  5018.5 2067.84  5019.0 2067.34  5036.4 2067.34
  5036.9 2067.84  5055.9 2073.15  5070.1 2078.23  5140.8 2105.52  5154.9 2111.95
  5169.1 2116.98  5178.7 2121.30  5183.2 2123.33  5208.0 2128.08  5211.5 2128.08
#Mann=7,-1,0
  4391.1     0.1       0  4589.7    0.07       0  4685.8     0.1       0
  4897.6    0.07       0  5018.5    0.05       0  5036.9    0.07       0
  5178.7     0.1       0
Bank Sta=5018.5,5036.9
Exp/Cntr=0.3,0.1

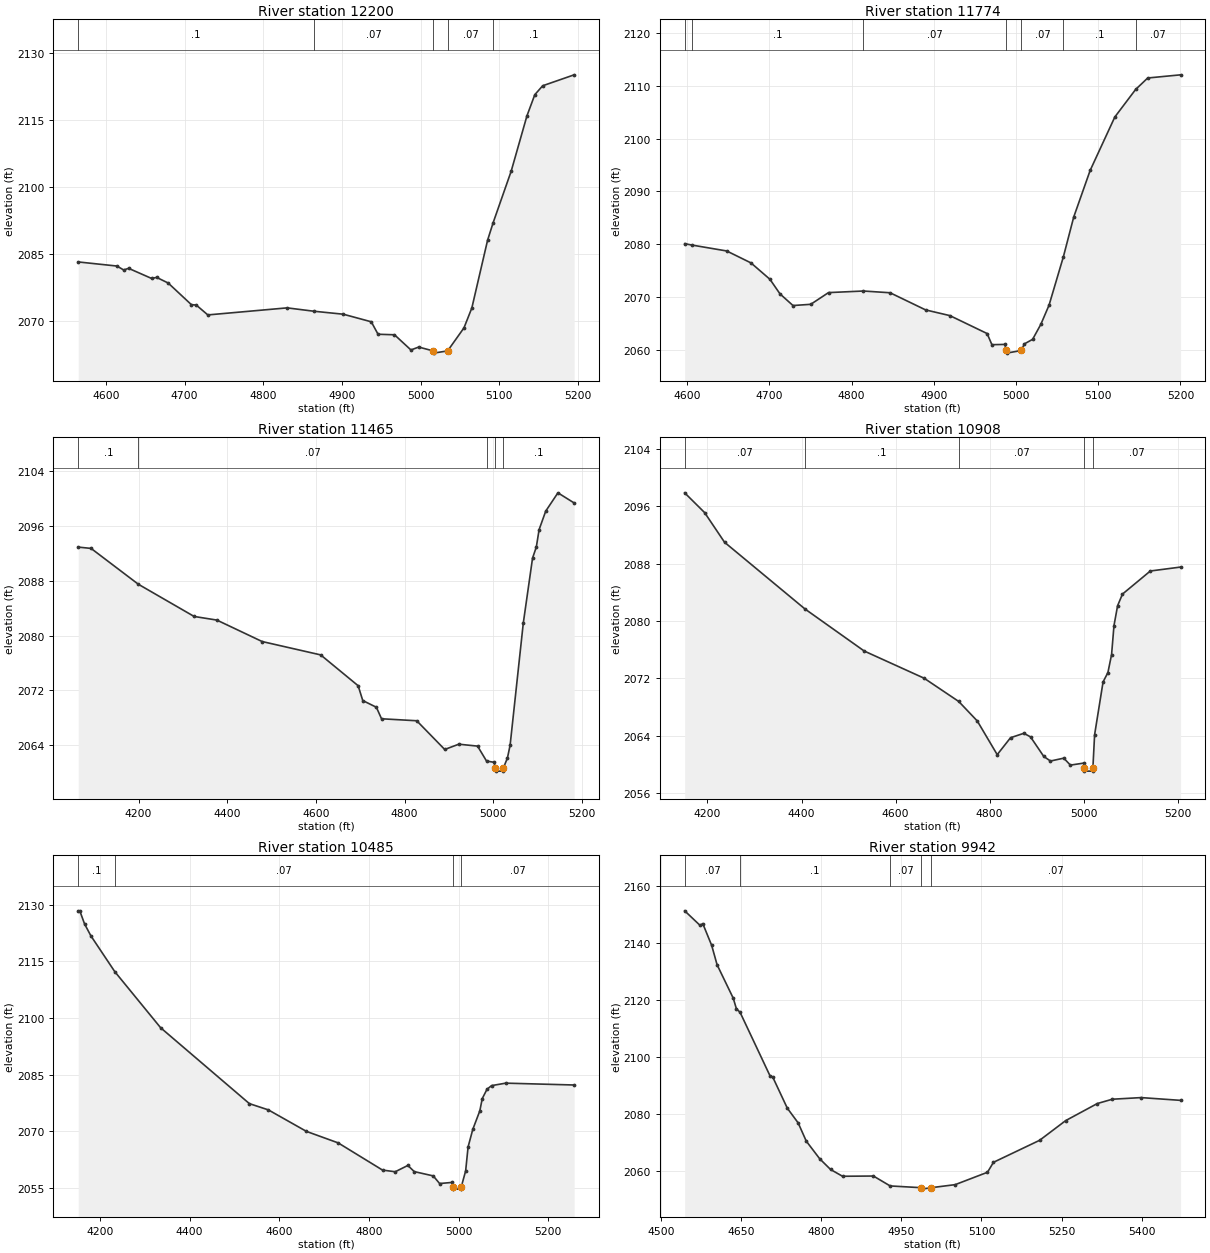
Type RM Length L Ch R = 1,12200,426,426,426
BEGIN DESCRIPTION:
Flat Rock Creek 2 25.0
END DESCRIPTION:
XS GIS Cut Line= 3
      1794774.97     13925125.04      1795025.00     13924775.00
      1795025.00     13924574.96
#Sta/Elev= 30
  4564.8 2083.17  4614.0 2082.25  4622.6 2081.37  4628.8 2081.74  4658.2 2079.46
  4664.4 2079.71  4679.1 2078.45  4708.6 2073.60  4714.8 2073.51  4729.5 2071.30
  4830.3 2072.88  4864.1 2072.13  4901.6 2071.46  4937.2 2069.76  4945.8 2066.97
  4966.7 2066.85  4987.6 2063.45  4997.5 2064.10  5015.8 2063.24  5016.3 2062.74
  5034.2 2063.24  5055.0 2068.40  5065.0 2072.86  5085.0 2088.04  5092.0 2091.93
  5115.0 2103.51  5135.0 2115.89  5145.0 2120.64  5155.0 2122.64  5195.0 2125.09
#Mann=5,-1,0
  4564.8     0.1       0  4864.1    0.07       0  5015.8    0.05       0
  5034.2    0.07       0  5092.0     0.1       0
Bank Sta=5015.8,5034.2
Exp/Cntr=0.3,0.1

Type RM Length L Ch R = 1,11774,309,309,309
BEGIN DESCRIPTION:
Flat Rock Creek 2 24.0
END DESCRIPTION:
XS GIS Cut Line= 3
      1795024.99     13925175.00      1795375.00     13924975.00
      1795375.00     13924775.02
#Sta/Elev= 30
  4597.1 2080.10  4606.3 2079.83  4648.2 2078.72  4677.7 2076.46  4700.8 2073.35
  4713.0 2070.59  4728.8 2068.38  4750.4 2068.61  4772.0 2070.83  4814.5 2071.13
  4846.9 2070.80  4890.1 2067.55  4919.6 2066.47  4964.9 2063.07  4970.7 2060.96
  4986.5 2061.01  4988.1 2059.86  4988.6 2059.36  5006.5 2059.86  5010.2 2061.11
  5020.2 2061.97  5030.2 2064.81  5040.2 2068.45  5057.6 2077.60  5070.2 2085.15
  5090.2 2093.99  5120.2 2104.11  5145.5 2109.33  5160.2 2111.50  5200.2 2112.10
#Mann=7,-1,0
  4597.1    0.07       0  4606.3     0.1       0  4814.5    0.07       0
  4988.1    0.05       0  5006.5    0.07       0  5057.6     0.1       0
  5145.5    0.07       0
Bank Sta=4988.1,5006.5
Exp/Cntr=0.3,0.1

Type RM Length L Ch R = 1,11465,557,557,557
BEGIN DESCRIPTION:
Flat Rock Creek 2 23.0
END DESCRIPTION:
XS GIS Cut Line= 3
      1794700.64     13925376.39      1795633.77     13925155.92
      1795725.00     13925025.00
#Sta/Elev= 30
  4064.0 2092.90  4093.0 2092.71  4199.6 2087.48  4325.4 2082.78  4376.7 2082.25
  4478.8 2079.12  4610.8 2077.17  4695.3 2072.67  4705.7 2070.51  4736.4 2069.53
  4748.0 2067.85  4827.4 2067.56  4890.5 2063.37  4922.3 2064.14  4964.6 2063.86
  4984.8 2061.68  5001.7 2061.50  5004.6 2060.71  5005.1 2060.21  5022.5 2060.21
  5023.0 2060.71  5031.9 2062.11  5038.0 2064.00  5067.7 2081.81  5088.6 2091.30
  5097.1 2092.91  5103.4 2095.46  5118.3 2098.15  5145.8 2100.82  5182.4 2099.34
#Mann=5,-1,0
  4064.0     0.1       0  4199.6    0.07       0  4984.8     0.1       0
  5004.6    0.05       0  5023.0     0.1       0
Bank Sta=5004.6,5023
Exp/Cntr=0.3,0.1

Type RM Length L Ch R = 1,10908,423,423,423
BEGIN DESCRIPTION:
Flat Rock Creek 2 22.0
END DESCRIPTION:
XS GIS Cut Line= 3
      1795375.03     13926124.97      1795975.00     13925525.00
      1796024.99     13925325.05
#Sta/Elev= 30
  4151.5 2097.87  4193.9 2095.11  4236.3 2090.97  4407.3 2081.66  4533.3 2075.79
  4660.6 2072.00  4734.3 2068.75  4773.7 2066.03  4816.1 2061.33  4844.4 2063.69
  4872.7 2064.31  4886.9 2063.81  4915.1 2061.08  4929.3 2060.44  4957.6 2060.84
  4971.7 2059.87  5000.0 2060.15  5001.0 2059.53  5001.5 2059.03  5019.1 2059.03
  5019.6 2059.53  5023.2 2064.11  5041.2 2071.48  5051.5 2072.79  5059.3 2075.30
  5064.4 2079.34  5072.1 2082.12  5082.5 2083.74  5141.7 2086.96  5206.1 2087.51
#Mann=5,-1,0
  4151.5    0.07       0  4407.3     0.1       0  4734.3    0.07       0
  5001.0    0.05       0  5019.6    0.07       0
Bank Sta=5001,5019.6
Exp/Cntr=0.3,0.1

Type RM Length L Ch R = 1,10485,543,543,543
BEGIN DESCRIPTION:
Flat Rock Creek 2 21.0
END DESCRIPTION:
XS GIS Cut Line= 3
      1795575.03     13926474.97      1796175.00     13925875.00
      1796419.31     13925792.95
#Sta/Elev= 30
  4151.5 2128.40  4155.0 2128.40  4165.6 2124.95  4179.7 2121.79  4233.1 2112.30
  4335.3 2097.46  4533.3 2077.37  4575.7 2075.71  4660.6 2070.02  4731.3 2066.98
  4830.3 2059.78  4858.6 2059.34  4886.8 2061.01  4901.0 2059.38  4943.4 2058.24
  4957.6 2056.22  4985.8 2056.52  4987.1 2055.24  4987.6 2054.74  5005.2 2054.74
  5005.7 2055.24  5015.7 2059.57  5021.1 2065.89  5031.6 2070.55  5047.3 2075.46
  5052.7 2078.70  5063.3 2081.17  5073.5 2082.14  5105.1 2082.79  5257.7 2082.30
#Mann=4,-1,0
  4151.5     0.1       0  4233.1    0.07       0  4987.1    0.05       0
  5005.7    0.07       0
Bank Sta=4987.1,5005.7
Exp/Cntr=0.3,0.1

Type RM Length L Ch R = 1,9942,383,383,383
BEGIN DESCRIPTION:
Flat Rock Creek 2 20.0
END DESCRIPTION:
XS GIS Cut Line= 3
      1796325.01     13926774.95      1796394.83     13926325.99
      1796496.99     13925862.68
#Sta/Elev= 30
  4544.2 2151.25  4573.1 2146.13  4578.1 2146.77  4594.8 2139.12  4604.9 2132.34
  4635.2 2120.61  4641.0 2116.96  4648.0 2115.66  4703.9 2093.46  4709.0 2093.03
  4736.4 2082.08  4756.7 2076.93  4771.9 2070.54  4797.2 2064.32  4817.4 2060.60
  4839.8 2058.22  4897.7 2058.30  4929.0 2054.83  4987.2 2054.21  4987.7 2053.71
  5005.8 2054.21  5050.8 2055.28  5111.3 2059.62  5122.5 2063.11  5208.9 2070.82
  5257.7 2077.72  5317.0 2083.71  5345.1 2085.22  5399.1 2085.79  5473.0 2084.82
#Mann=5,-1,0
  4544.2    0.07       0  4648.0     0.1       0  4929.0    0.07       0
  4987.2    0.05       0  5005.8    0.07       0
Bank Sta=4987.2,5005.8
Exp/Cntr=0.3,0.1

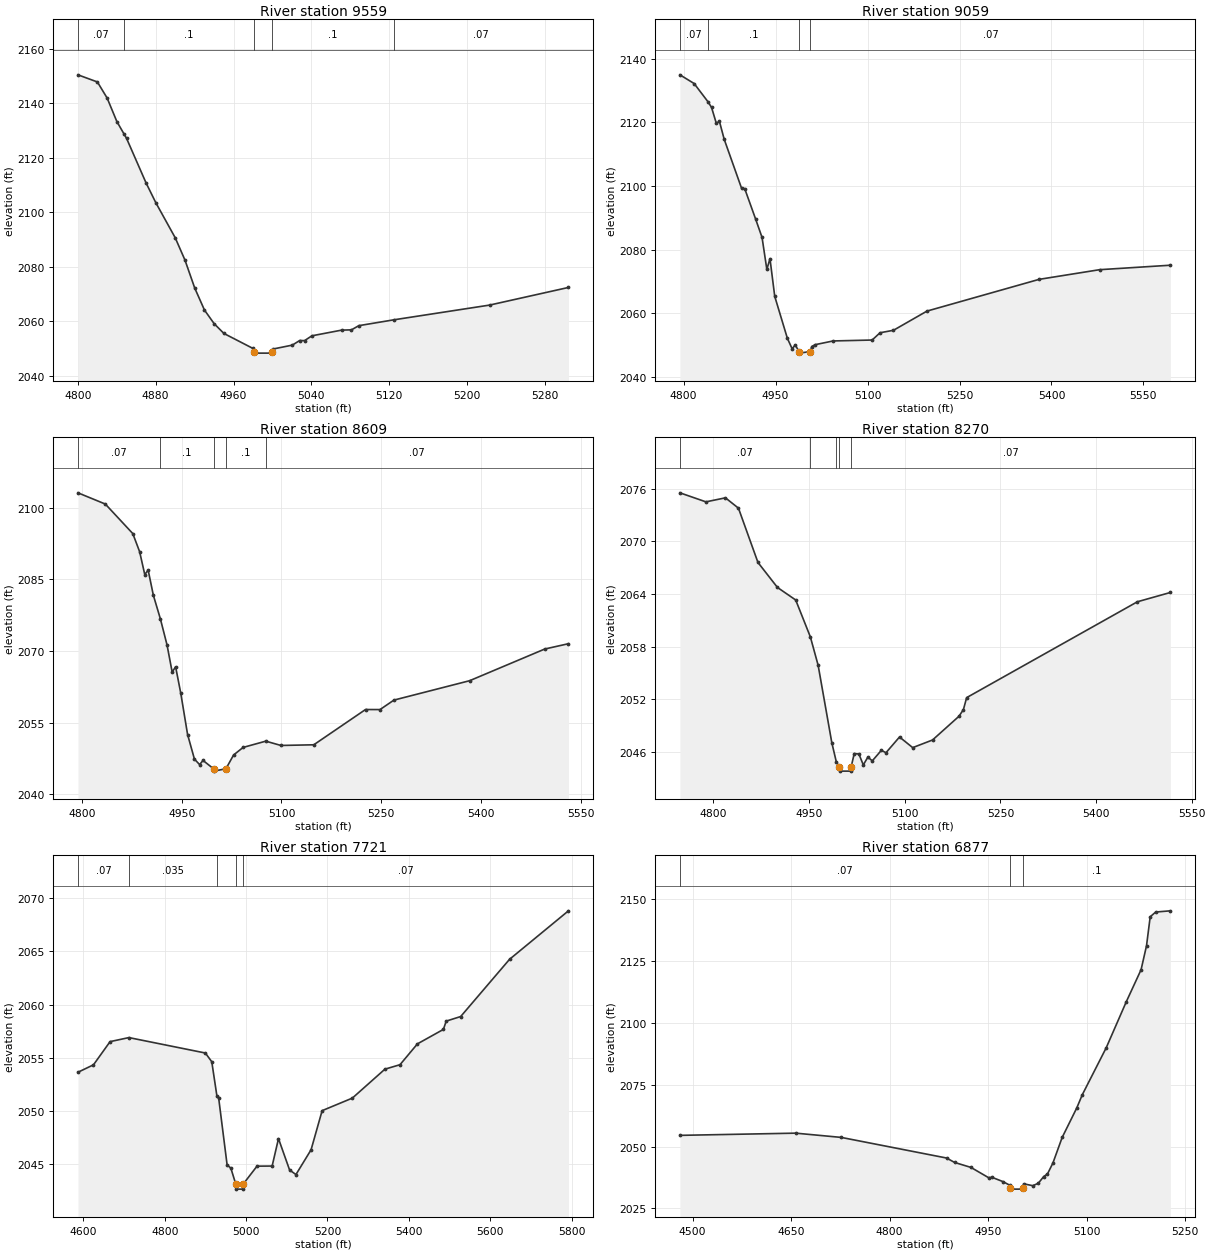
Type RM Length L Ch R = 1,9559,500,500,500
BEGIN DESCRIPTION:
Flat Rock Creek 2 19.0
END DESCRIPTION:
XS GIS Cut Line= 3
      1796675.00     13926725.00      1796675.00     13926525.00
      1796724.99     13926225.03
#Sta/Elev= 30
  4800.1 2150.37  4820.1 2147.75  4830.1 2141.85  4840.1 2133.23  4847.5 2128.64
  4850.1 2127.03  4870.1 2110.72  4880.1 2103.48  4900.1 2090.57  4910.1 2082.40
  4920.1 2072.17  4930.1 2064.09  4940.1 2059.07  4950.1 2055.49  4980.1 2049.97
  4980.8 2048.77  4981.3 2048.27  4998.9 2048.27  4999.4 2048.77  5000.1 2049.74
  5020.4 2051.21  5028.0 2052.89  5033.0 2052.86  5040.6 2054.63  5071.1 2056.71
  5081.2 2056.81  5088.8 2058.35  5125.1 2060.51  5223.1 2065.89  5304.2 2072.36
#Mann=5,-1,0
  4800.1    0.07       0  4847.5     0.1       0  4980.8    0.05       0
  4999.4     0.1       0  5125.1    0.07       0
Bank Sta=4980.8,4999.4
Exp/Cntr=0.3,0.1

Type RM Length L Ch R = 1,9059,450,450,450
BEGIN DESCRIPTION:
Flat Rock Creek 2 18.0
END DESCRIPTION:
XS GIS Cut Line= 3
      1797124.99     13926725.03      1797175.00     13926525.00
      1796934.13     13925982.02
#Sta/Elev= 30
  4793.9 2134.98  4817.1 2132.24  4839.5 2126.55  4845.5 2124.72  4853.2 2119.77
  4858.4 2120.30  4866.1 2114.72  4894.4 2099.33  4899.6 2099.17  4917.6 2089.49
  4927.9 2083.81  4935.7 2073.75  4940.8 2077.15  4948.6 2065.26  4969.2 2052.08
  4976.9 2048.81  4982.1 2049.98  4988.2 2047.92  4988.7 2047.42  5006.9 2047.92
  5009.0 2049.50  5014.5 2050.08  5043.8 2051.25  5107.5 2051.54  5120.4 2053.83
  5142.3 2054.61  5197.0 2060.65  5379.9 2070.63  5478.5 2073.67  5594.1 2075.08
#Mann=4,-1,0
  4793.9    0.07       0  4839.5     0.1       0  4988.2    0.05       0
  5006.9    0.07       0
Bank Sta=4988.2,5006.9
Exp/Cntr=0.3,0.1

Type RM Length L Ch R = 1,8609,339,339,339
BEGIN DESCRIPTION:
Flat Rock Creek 2 17.0
END DESCRIPTION:
XS GIS Cut Line= 3
      1797525.00     13926574.99      1797575.00     13926375.00
      1797174.96     13926024.97
#Sta/Elev= 30
  4793.9 2103.11  4835.1 2100.76  4876.4 2094.58  4886.7 2090.78  4894.4 2086.01
  4899.5 2086.94  4907.3 2081.69  4917.9 2076.73  4927.9 2071.28  4935.6 2065.61
  4940.8 2066.71  4948.5 2061.22  4958.8 2052.54  4969.1 2047.40  4976.9 2046.24
  4982.0 2047.12  4997.8 2045.38  4998.3 2044.88  5016.5 2045.38  5028.0 2048.26
  5042.3 2049.84  5076.4 2051.15  5099.2 2050.25  5148.6 2050.39  5226.4 2057.77
  5248.2 2057.76  5269.1 2059.74  5383.0 2063.80  5496.0 2070.43  5531.6 2071.54
#Mann=5,-1,0
  4793.9    0.07       0  4917.9     0.1       0  4997.8    0.05       0
  5016.5     0.1       0  5076.4    0.07       0
Bank Sta=4997.8,5016.5
Exp/Cntr=0.3,0.1

Type RM Length L Ch R = 1,8270,549,549,549
BEGIN DESCRIPTION:
Flat Rock Creek 2 16.0
END DESCRIPTION:
XS GIS Cut Line= 4
      1797875.00     13926425.00      1797908.27     13926258.66
      1797794.92     13926139.52      1797375.03     13926025.01
#Sta/Elev= 30
  4747.4 2075.54  4788.2 2074.51  4818.8 2074.97  4839.2 2073.79  4869.8 2067.60
  4900.4 2064.75  4929.0 2063.32  4952.0 2059.11  4964.2 2055.87  4985.6 2047.06
  4992.7 2044.86  4997.3 2044.31  4997.8 2043.81  5015.5 2043.81  5016.0 2044.31
  5020.8 2045.81  5028.1 2045.76  5035.0 2044.52  5042.2 2045.41  5049.1 2044.98
  5063.3 2046.18  5070.6 2045.91  5091.8 2047.70  5112.5 2046.49  5143.6 2047.36
  5185.0 2050.06  5192.0 2050.82  5197.1 2052.19  5464.9 2063.12  5516.7 2064.18
#Mann=5,-1,0
  4747.4    0.07       0  4952.0     0.1       0  4992.7    0.07       0
  4997.3    0.05       0  5016.0    0.07       0
Bank Sta=4997.3,5016
Exp/Cntr=0.3,0.1

Type RM Length L Ch R = 1,7721,844,844,844
BEGIN DESCRIPTION:
Flat Rock Creek 2 16.1
END DESCRIPTION:
XS GIS Cut Line= 4
      1798352.79     13926272.50      1798286.85     13925932.85
      1798046.26     13925524.12      1797779.48     13925245.81
#Sta/Elev= 30
  4586.6 2053.63  4624.8 2054.33  4665.6 2056.51  4711.9 2056.89  4899.8 2055.44
  4915.6 2054.62  4928.1 2051.43  4932.6 2051.19  4953.3 2044.92  4962.5 2044.61
  4974.4 2043.14  4974.9 2042.64  4992.9 2042.64  4993.4 2043.14  5026.8 2044.80
  5064.0 2044.81  5079.6 2047.39  5106.9 2044.44  5122.5 2044.01  5159.7 2046.34
  5186.9 2050.02  5261.2 2051.20  5341.2 2053.92  5378.3 2054.34  5421.2 2056.30
  5485.0 2057.66  5491.9 2058.44  5527.5 2058.87  5647.6 2064.25  5792.4 2068.81
#Mann=5,-1,0
  4586.6    0.07       0  4711.9   0.035       0  4928.1    0.07       0
  4974.4    0.05       0  4993.4    0.07       0
Bank Sta=4974.4,4993.4
Exp/Cntr=0.3,0.1

Type RM Length L Ch R = 1,6877,469,469,469
BEGIN DESCRIPTION:
Flat Rock Creek 2 15.0
END DESCRIPTION:
XS GIS Cut Line= 4
      1798727.78     13925876.70      1798756.82     13925741.38
      1798875.00     13925375.00      1798975.01     13925174.98
#Sta/Elev= 30
  4480.7 2054.56  4657.1 2055.45  4726.4 2053.73  4886.7 2045.40  4899.0 2043.61
  4924.0 2041.59  4950.7 2037.46  4956.0 2037.59  4972.5 2035.88  4982.8 2034.43
  4984.0 2033.32  4984.5 2032.82  5002.6 2032.82  5003.1 2033.32  5004.1 2034.97
  5018.0 2034.22  5026.4 2035.16  5034.8 2037.92  5040.4 2038.92  5048.8 2043.41
  5062.8 2053.70  5085.1 2065.66  5093.5 2070.99  5129.9 2089.96  5160.6 2108.65
  5183.0 2121.53  5191.3 2131.23  5196.9 2142.93  5205.3 2144.86  5227.7 2145.34
#Mann=3,-1,0
  4480.7    0.07       0  4984.0    0.05       0  5003.1     0.1       0
Bank Sta=4984,5003.1
Exp/Cntr=0.3,0.1