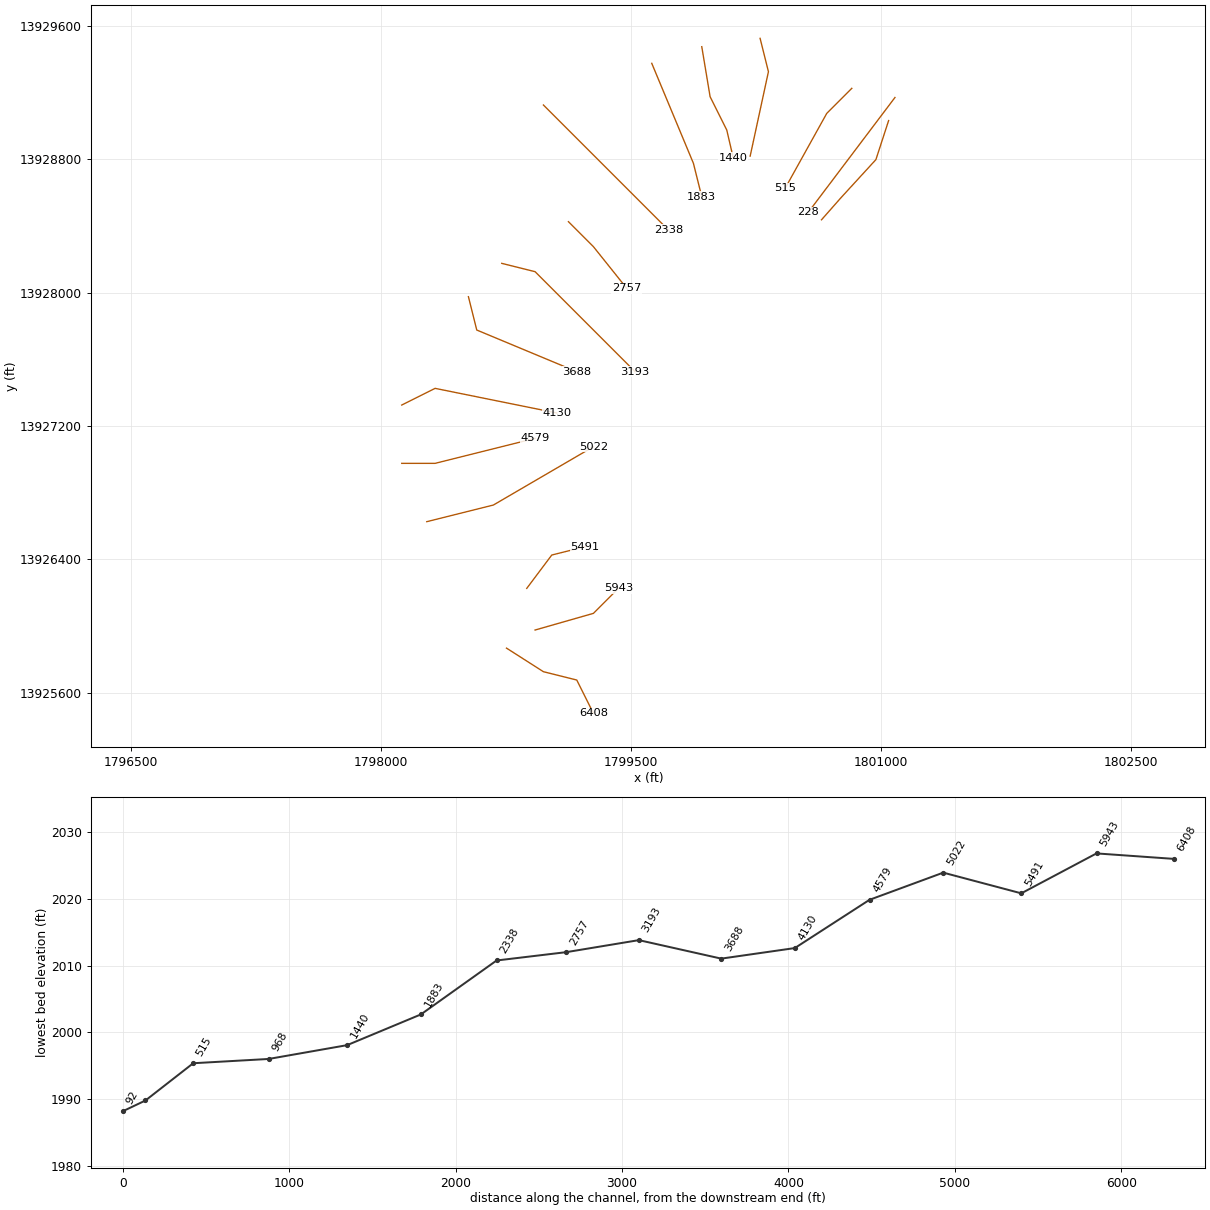
HEC-RAS study Flat Rock Creek 2.prj: Flat Rock Creek 2 Base Level Engineering

--- Flat Rock Creek 2.g01 (geometry) --- (continued)

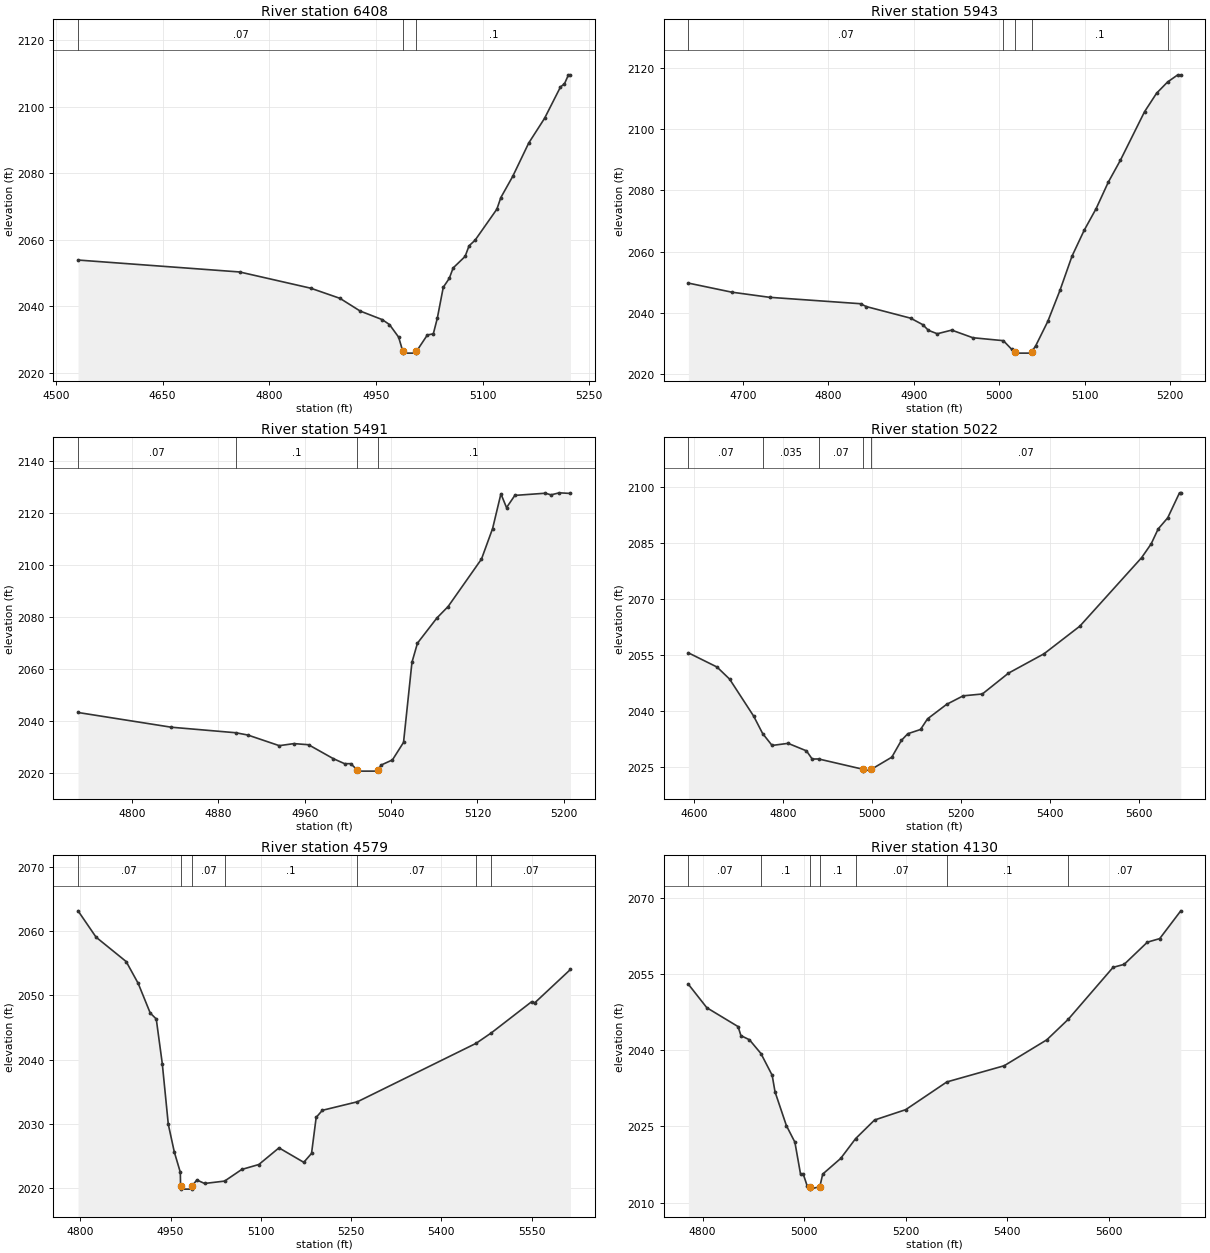
Type RM Length L Ch R = 1,6408,465,465,465
BEGIN DESCRIPTION:
Flat Rock Creek 2 14.0
END DESCRIPTION:
XS GIS Cut Line= 4
      1798753.43     13925866.50      1798975.00     13925725.00
      1799175.00     13925675.00      1799275.02     13925474.96
#Sta/Elev= 30
  4531.0 2053.94  4758.3 2050.36  4858.3 2045.49  4899.5 2042.44  4927.9 2038.63
  4958.8 2036.07  4969.1 2034.58  4982.0 2030.80  4987.9 2026.50  4988.4 2026.00
  5006.5 2026.00  5007.0 2026.50  5022.4 2031.45  5030.8 2031.79  5036.4 2036.46
  5044.8 2045.77  5053.2 2048.42  5058.7 2051.57  5075.5 2055.02  5081.1 2058.22
  5089.5 2059.88  5120.2 2069.21  5125.8 2072.70  5142.6 2079.09  5165.0 2089.06
  5187.3 2096.48  5209.7 2105.90  5215.3 2106.83  5220.9 2109.53  5223.7 2109.53
#Mann=3,-1,0
  4531.0    0.07       0  4987.9    0.05       0  5007.0     0.1       0
Bank Sta=4987.9,5007
Exp/Cntr=0.3,0.1

Type RM Length L Ch R = 1,5943,452,452,452
BEGIN DESCRIPTION:
Flat Rock Creek 2 13.0
END DESCRIPTION:
XS GIS Cut Line= 3
      1798925.02     13925975.01      1799275.00     13926075.00
      1799424.99     13926224.99
#Sta/Elev= 30
  4636.3 2049.70  4687.0 2046.74  4731.2 2045.06  4837.8 2042.96  4844.3 2042.04
  4896.3 2038.24  4910.6 2036.11  4917.1 2034.27  4927.5 2033.15  4944.4 2034.34
  4969.1 2031.85  5004.8 2030.89  5014.4 2028.11  5019.0 2027.32  5019.5 2026.82
  5037.6 2026.82  5038.1 2027.32  5042.7 2029.24  5056.8 2037.19  5071.0 2047.30
  5085.1 2058.49  5099.3 2066.93  5113.4 2074.07  5127.6 2082.70  5141.7 2089.82
  5170.0 2105.70  5184.1 2111.75  5196.9 2115.40  5208.9 2117.75  5212.4 2117.75
#Mann=5,-1,0
  4636.3    0.07       0  5004.8     0.1       0  5019.0    0.05       0
  5038.1     0.1       0  5196.9    0.07       0
Bank Sta=5019,5038.1
Exp/Cntr=0.3,0.1

Type RM Length L Ch R = 1,5491,469,469,469
BEGIN DESCRIPTION:
Flat Rock Creek 2 12.0
END DESCRIPTION:
XS GIS Cut Line= 3
      1798875.01     13926225.01      1799025.00     13926425.00
      1799224.96     13926474.99
#Sta/Elev= 30
  4750.0 2043.34  4836.4 2037.69  4896.1 2035.57  4907.3 2034.69  4936.4 2030.61
  4950.0 2031.40  4963.5 2030.97  4986.4 2025.64  4996.9 2023.70  5002.6 2023.70
  5008.5 2021.34  5009.0 2020.84  5027.1 2020.84  5027.6 2021.34  5030.9 2023.20
  5041.2 2025.14  5051.5 2031.87  5059.3 2062.60  5064.4 2069.95  5082.4 2079.61
  5092.8 2084.01  5123.7 2102.22  5134.0 2113.94  5141.7 2127.26  5146.9 2121.96
  5154.6 2126.65  5182.9 2127.49  5188.1 2126.86  5195.8 2127.64  5206.1 2127.41
#Mann=4,-1,0
  4750.0    0.07       0  4896.1     0.1       0  5008.5    0.05       0
  5027.6     0.1       0
Bank Sta=5008.5,5027.6
Exp/Cntr=0.3,0.1

Type RM Length L Ch R = 1,5022,443,443,443
BEGIN DESCRIPTION:
Flat Rock Creek 2 11.0
END DESCRIPTION:
XS GIS Cut Line= 3
      1798275.04     13926625.01      1798675.00     13926725.00
      1799275.01     13927075.00
#Sta/Elev= 30
  4587.5 2055.62  4651.9 2051.82  4680.2 2048.58  4734.3 2038.66  4754.4 2034.01
  4775.6 2030.82  4811.7 2031.38  4852.9 2029.37  4865.8 2027.18  4880.2 2027.20
  4979.9 2024.44  4980.4 2023.94  4999.0 2024.44  5044.8 2027.68  5066.3 2032.17
  5080.8 2033.96  5109.3 2035.09  5125.1 2037.95  5168.1 2041.83  5205.3 2044.11
  5248.3 2044.60  5307.0 2050.18  5387.2 2055.39  5467.4 2062.76  5606.3 2081.11
  5627.8 2084.81  5643.5 2088.80  5665.0 2091.78  5691.5 2098.48  5694.4 2098.48
#Mann=5,-1,0
  4587.5    0.07       0  4754.4   0.035       0  4880.2    0.07       0
  4979.9    0.05       0  4999.0    0.07       0
Bank Sta=4979.9,4999
Exp/Cntr=0.3,0.1

Type RM Length L Ch R = 1,4579,449,449,449
BEGIN DESCRIPTION:
Flat Rock Creek 2 10.0
END DESCRIPTION:
XS GIS Cut Line= 3
      1798125.03     13926975.00      1798325.00     13926975.00
      1798924.96     13927124.99
#Sta/Elev= 30
  4796.3 2063.16  4826.3 2059.06  4876.3 2055.27  4896.3 2051.87  4916.3 2047.26
  4926.3 2046.34  4936.3 2039.41  4946.3 2029.96  4956.3 2025.65  4966.3 2022.49
  4966.7 2020.37  4967.2 2019.87  4985.3 2019.87  4985.8 2020.37  4993.8 2021.29
  5006.6 2020.75  5039.9 2021.12  5068.4 2022.93  5096.8 2023.70  5130.3 2026.29
  5171.5 2024.04  5184.4 2025.43  5192.1 2031.03  5202.4 2032.13  5260.7 2033.46
  5457.9 2042.55  5483.3 2044.18  5550.3 2049.03  5555.5 2048.86  5614.7 2054.04
#Mann=7,-1,0
  4796.3    0.07       0  4966.7    0.05       0  4985.8    0.07       0
  5039.9     0.1       0  5260.7    0.07       0  5457.9     0.1       0
  5483.3    0.07       0
Bank Sta=4966.7,4985.8
Exp/Cntr=0.3,0.1

Type RM Length L Ch R = 1,4130,442,442,442
BEGIN DESCRIPTION:
Flat Rock Creek 2 9.0
END DESCRIPTION:
XS GIS Cut Line= 3
      1798125.00     13927325.00      1798325.00     13927425.00
      1799055.70     13927277.21
#Sta/Elev= 30
  4772.2 2053.04  4808.5 2048.41  4870.0 2044.69  4875.6 2042.91  4892.4 2042.09
  4915.0 2039.38  4937.1 2035.09  4942.7 2031.83  4965.1 2025.16  4981.8 2021.90
  4993.0 2015.56  4998.4 2015.56  5006.0 2013.27  5011.5 2013.14  5012.0 2012.64
  5030.9 2013.14  5036.6 2015.61  5071.9 2018.69  5101.3 2022.60  5138.6 2026.27
  5199.9 2028.31  5280.9 2033.78  5393.7 2036.97  5477.7 2042.09  5519.7 2046.12
  5608.0 2056.37  5629.9 2056.97  5675.5 2061.34  5699.8 2062.04  5741.3 2067.52
#Mann=7,-1,0
  4772.2    0.07       0  4915.0     0.1       0  5011.5    0.05       0
  5030.9     0.1       0  5101.3    0.07       0  5280.9     0.1       0
  5519.7    0.07       0
Bank Sta=5011.5,5030.9
Exp/Cntr=0.3,0.1

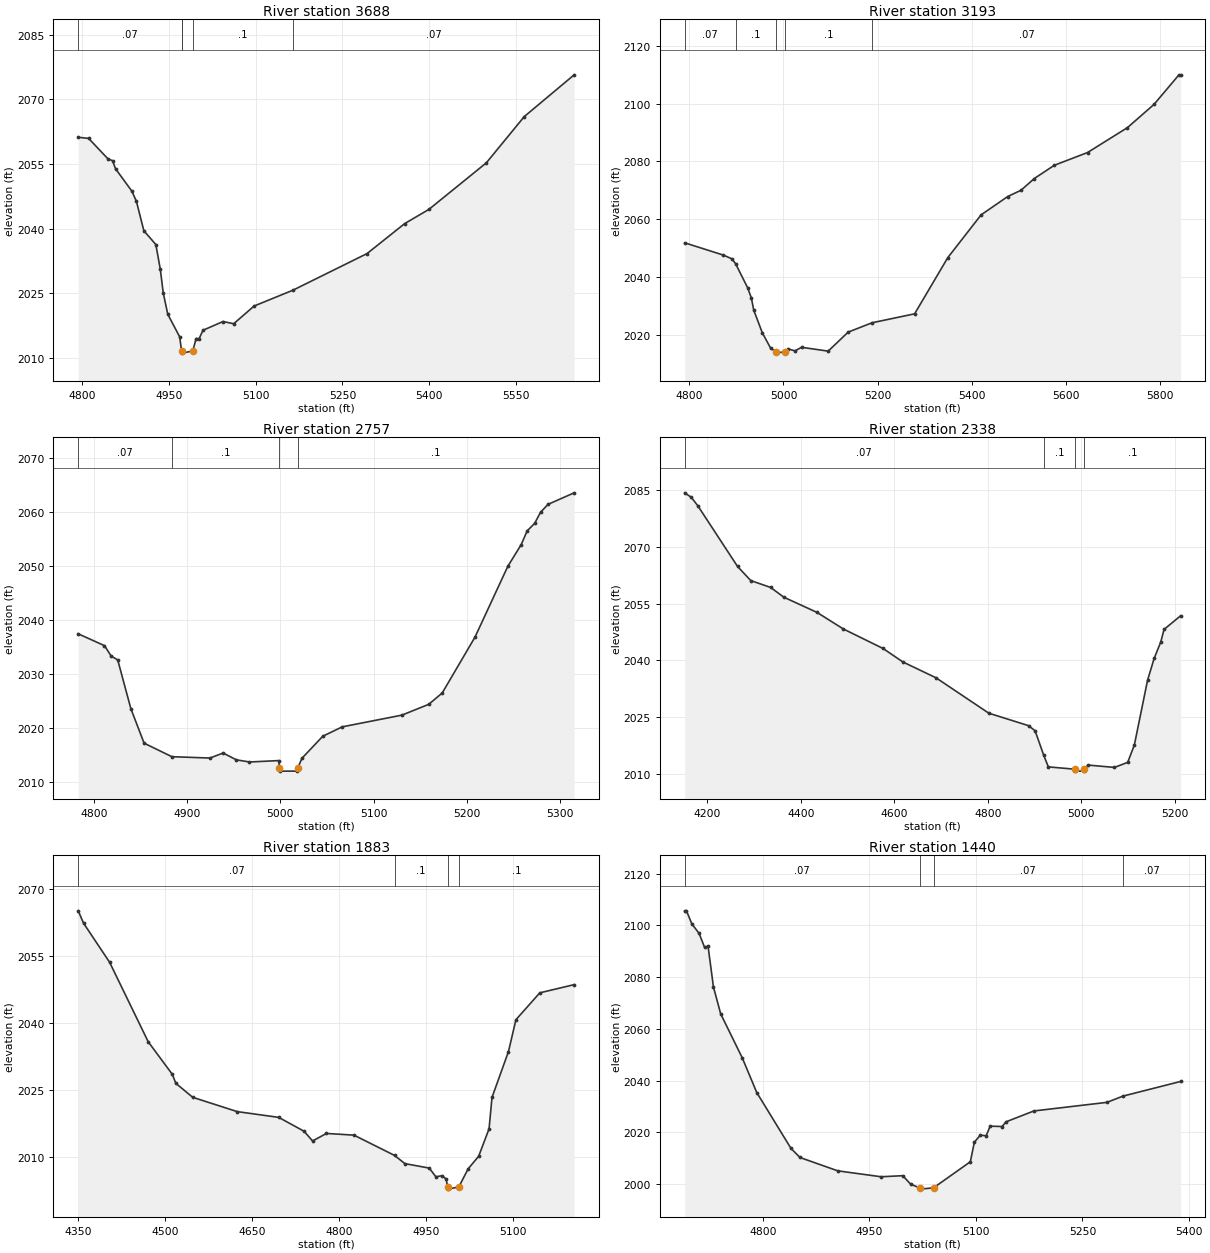
Type RM Length L Ch R = 1,3688,495,495,495
BEGIN DESCRIPTION:
Flat Rock Creek 2 8.0
END DESCRIPTION:
XS GIS Cut Line= 3
      1798525.01     13927974.96      1798575.00     13927775.00
      1799174.98     13927525.01
#Sta/Elev= 30
  4793.9 2061.21  4811.9 2060.95  4845.4 2056.17  4853.1 2055.78  4858.3 2053.90
  4886.6 2048.68  4894.4 2046.31  4907.2 2039.50  4927.9 2036.29  4935.6 2030.55
  4940.7 2025.03  4948.5 2020.09  4969.1 2014.83  4972.2 2011.66  4972.3 2011.56
  4972.8 2011.06  4991.7 2011.56  4997.4 2014.44  5002.7 2014.44  5009.2 2016.37
  5043.9 2018.40  5062.3 2017.89  5097.5 2022.00  5164.7 2025.69  5292.5 2034.19
  5357.5 2041.16  5399.2 2044.45  5498.4 2055.27  5563.9 2066.02  5650.0 2075.72
#Mann=5,-1,0
  4793.9    0.07       0  4972.2     0.1       0  4972.3    0.05       0
  4991.7     0.1       0  5164.7    0.07       0
Bank Sta=4972.3,4991.7
Exp/Cntr=0.3,0.1

Type RM Length L Ch R = 1,3193,436,436,436
BEGIN DESCRIPTION:
Flat Rock Creek 2 7.0
END DESCRIPTION:
XS GIS Cut Line= 3
      1798724.97     13928175.01      1798925.00     13928125.00
      1799524.99     13927525.01
#Sta/Elev= 30
  4789.9 2051.91  4872.4 2047.66  4890.4 2046.38  4898.3 2044.67  4923.9 2036.36
  4931.7 2032.88  4936.8 2028.66  4954.9 2020.88  4972.9 2015.48  4983.8 2014.33
  4984.3 2013.83  5003.2 2014.33  5010.2 2015.26  5024.4 2014.62  5038.5 2015.84
  5095.1 2014.52  5137.5 2021.08  5188.4 2024.31  5278.9 2027.40  5349.6 2046.83
  5420.3 2061.56  5476.9 2067.89  5505.2 2070.06  5533.5 2074.11  5575.9 2078.67
  5646.6 2083.07  5731.5 2091.67  5788.0 2099.69  5841.1 2109.90  5844.6 2109.90
#Mann=5,-1,0
  4789.9    0.07       0  4898.3     0.1       0  4983.8    0.05       0
  5003.2     0.1       0  5188.4    0.07       0
Bank Sta=4983.8,5003.2
Exp/Cntr=0.3,0.1

Type RM Length L Ch R = 1,2757,419,419,419
BEGIN DESCRIPTION:
Flat Rock Creek 2 6.0
END DESCRIPTION:
XS GIS Cut Line= 3
      1799125.03     13928424.97      1799275.00     13928275.00
      1799474.97     13928025.03
#Sta/Elev= 30
  4783.1 2037.43  4811.3 2035.24  4818.4 2033.33  4825.5 2032.60  4839.6 2023.58
  4853.8 2017.20  4883.6 2014.70  4924.5 2014.45  4938.6 2015.38  4952.8 2014.12
  4966.9 2013.72  4998.4 2013.98  4999.0 2012.53  4999.5 2012.03  5018.0 2012.03
  5018.5 2012.53  5023.2 2014.41  5045.6 2018.49  5066.4 2020.22  5130.5 2022.39
  5159.3 2024.39  5173.7 2026.48  5208.9 2036.82  5244.1 2049.91  5258.5 2053.94
  5264.9 2056.48  5272.9 2057.86  5279.3 2059.93  5287.3 2061.38  5315.3 2063.51
#Mann=4,-1,0
  4783.1    0.07       0  4883.6     0.1       0  4999.0    0.05       0
  5018.5     0.1       0
Bank Sta=4999,5018.5
Exp/Cntr=0.3,0.1

Type RM Length L Ch R = 1,2338,455,455,455
BEGIN DESCRIPTION:
Flat Rock Creek 2 5.0
END DESCRIPTION:
XS GIS Cut Line= 3
      1798974.99     13929125.01      1799575.00     13928525.00
      1799725.02     13928374.98
#Sta/Elev= 30
  4151.7 2084.28  4165.9 2083.09  4180.0 2080.82  4264.8 2064.83  4293.1 2061.10
  4335.6 2059.29  4363.8 2056.71  4434.6 2052.71  4491.1 2048.32  4576.0 2043.17
  4618.4 2039.61  4689.1 2035.44  4802.2 2026.08  4887.1 2022.79  4901.2 2021.44
  4919.2 2015.11  4929.5 2011.90  4987.0 2011.28  4987.5 2010.78  5006.0 2010.78
  5006.5 2011.28  5014.4 2012.38  5070.9 2011.76  5099.2 2013.09  5113.4 2017.65
  5141.7 2034.78  5155.8 2040.55  5169.9 2044.87  5177.0 2048.21  5212.4 2051.81
#Mann=4,-1,0
  4151.7    0.07       0  4919.2     0.1       0  4987.0    0.05       0
  5006.5     0.1       0
Bank Sta=4987,5006.5
Exp/Cntr=0.3,0.1

Type RM Length L Ch R = 1,1883,443,443,443
BEGIN DESCRIPTION:
Flat Rock Creek 2 4.0
END DESCRIPTION:
XS GIS Cut Line= 3
      1799624.99     13929375.02      1799875.00     13928775.00
      1799925.01     13928574.98
#Sta/Elev= 30
  4349.9 2065.18  4359.1 2062.41  4404.1 2053.63  4470.7 2035.79  4512.4 2028.47
  4518.4 2026.46  4547.6 2023.31  4624.5 2020.10  4696.0 2018.81  4739.9 2015.69
  4754.5 2013.51  4778.4 2015.20  4826.0 2014.82  4896.0 2010.27  4913.8 2008.43
  4956.0 2007.42  4967.4 2005.46  4978.3 2005.73  4985.3 2004.93  4987.5 2003.20
  4988.0 2002.70  5007.0 2003.20  5023.1 2007.26  5041.2 2010.07  5059.2 2016.24
  5064.3 2023.30  5092.7 2033.58  5105.6 2040.74  5146.8 2046.77  5206.1 2048.61
#Mann=4,-1,0
  4349.9    0.07       0  4896.0     0.1       0  4987.5    0.05       0
  5007.0     0.1       0
Bank Sta=4987.5,5007
Exp/Cntr=0.3,0.1

Type RM Length L Ch R = 1,1440,472,472,472
BEGIN DESCRIPTION:
Flat Rock Creek 2 3.0
END DESCRIPTION:
XS GIS Cut Line= 4
      1799925.00     13929474.99      1799975.00     13929175.00
      1800075.00     13928975.00      1800113.54     13928809.26
#Sta/Elev= 30
  4690.2 2105.65  4692.7 2105.65  4700.3 2100.61  4710.5 2096.92  4718.1 2091.59
  4723.1 2091.95  4730.7 2076.21  4740.9 2065.81  4771.3 2048.79  4791.6 2035.44
  4839.7 2013.88  4852.4 2010.33  4905.6 2005.17  4966.5 2002.88  4997.1 2003.29
  5008.3 1999.98  5020.9 1998.60  5021.4 1998.10  5040.4 1998.60  5092.2 2008.68
  5097.8 2016.21  5106.1 2018.93  5114.5 2018.75  5120.1 2022.43  5136.9 2022.30
  5142.5 2024.12  5181.6 2028.31  5284.4 2031.63  5307.1 2034.06  5388.1 2039.71
#Mann=4,-1,0
  4690.2    0.07       0  5020.9    0.05       0  5040.4    0.07       0
  5307.1    0.07       0
Bank Sta=5020.9,5040.4
Exp/Cntr=0.3,0.1

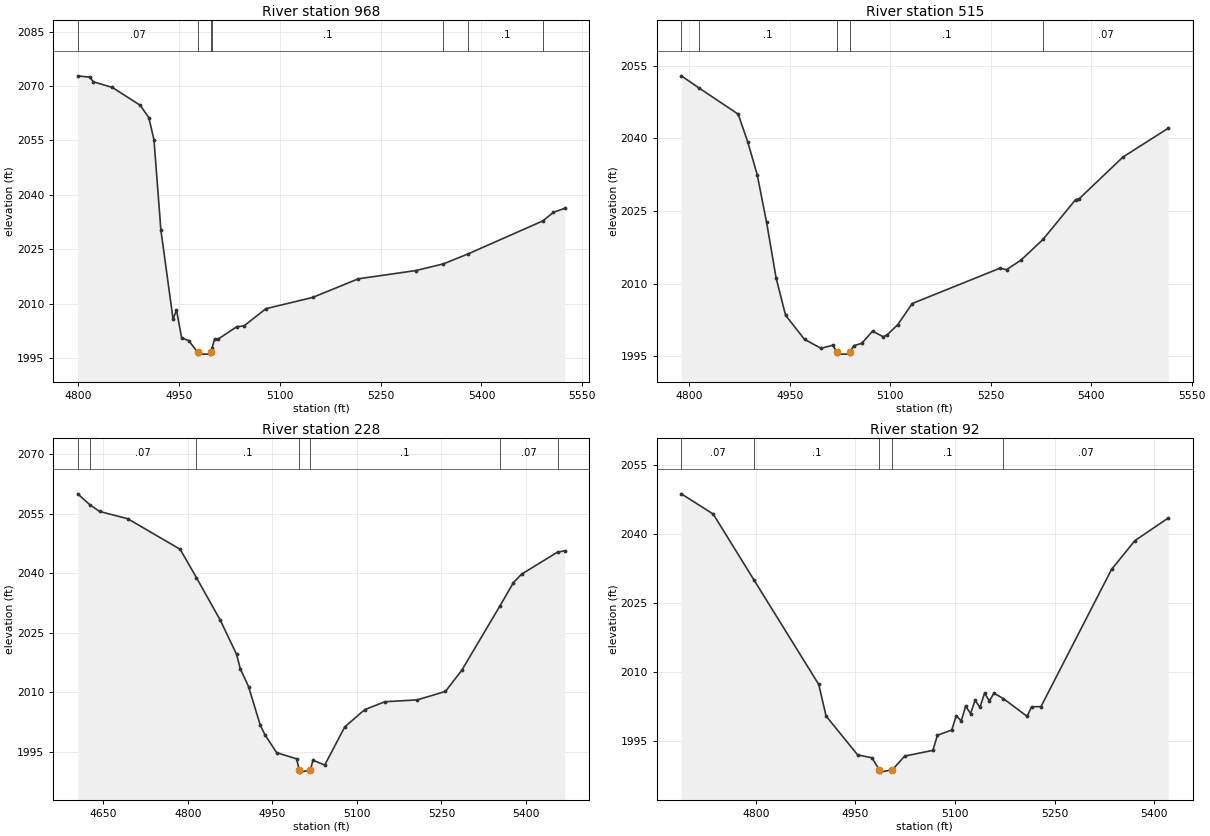
Type RM Length L Ch R = 1,968,453,453,453
BEGIN DESCRIPTION:
Flat Rock Creek 2 2.0
END DESCRIPTION:
XS GIS Cut Line= 3
      1800274.99     13929525.03      1800325.00     13929325.00
      1800215.42     13928818.51
#Sta/Elev= 30
  4799.3 2072.83  4817.4 2072.43  4822.5 2071.19  4850.9 2069.61  4892.1 2064.72
  4905.0 2061.32  4912.7 2055.20  4923.0 2030.24  4941.1 2005.70  4946.2 2008.21
  4953.9 2000.48  4964.3 1999.77  4977.7 1996.53  4978.2 1996.03  4996.7 1996.03
  4997.2 1996.53  4999.1 1997.74  5002.9 2000.16  5008.0 2000.16  5036.2 2003.63
  5046.4 2003.79  5079.3 2008.57  5148.7 2011.67  5216.8 2016.82  5302.2 2019.09
  5343.4 2020.94  5380.2 2023.70  5491.4 2032.81  5507.0 2035.16  5523.7 2036.26
#Mann=7,-1,0
  4799.3    0.07       0  4977.7    0.05       0  4997.2    0.07       0
  4999.1     0.1       0  5343.4    0.07       0  5380.2     0.1       0
  5491.4    0.07       0
Bank Sta=4977.7,4997.2
Exp/Cntr=0.3,0.1

Type RM Length L Ch R = 1,515,287,287,287
BEGIN DESCRIPTION:
Flat Rock Creek 2 1.0
END DESCRIPTION:
XS GIS Cut Line= 3
      1800825.01     13929225.01      1800675.00     13929075.00
      1800425.01     13928625.02
#Sta/Elev= 30
  4788.1 2052.96  4815.2 2050.38  4873.0 2045.03  4887.1 2039.34  4901.3 2032.54
  4915.4 2022.63  4929.5 2011.20  4943.7 2003.43  4972.0 1998.44  4996.7 1996.60
  5014.0 1997.22  5020.2 1995.89  5020.7 1995.39  5039.3 1995.39  5039.8 1995.89
  5046.0 1997.16  5057.4 1997.62  5073.5 2000.14  5089.5 1998.99  5095.2 1999.36
  5111.2 2001.49  5132.9 2005.86  5263.4 2013.15  5273.7 2012.87  5295.4 2014.86
  5328.2 2019.14  5376.6 2027.33  5382.3 2027.56  5447.5 2036.17  5515.0 2042.12
#Mann=5,-1,0
  4788.1    0.07       0  4815.2     0.1       0  5020.2    0.05       0
  5039.8     0.1       0  5328.2    0.07       0
Bank Sta=5020.2,5039.8
Exp/Cntr=0.3,0.1

Type RM Length L Ch R = 1,228,136,136,136
BEGIN DESCRIPTION:
Flat Rock Creek 2 0.0
END DESCRIPTION:
XS GIS Cut Line= 2
      1801084.10     13929170.08      1800563.21     13928480.25
#Sta/Elev= 30
  4604.4 2060.05  4626.1 2057.26  4643.2 2055.60  4693.2 2053.76  4786.2 2046.05
  4815.0 2038.93  4857.6 2028.12  4886.4 2019.52  4893.0 2015.89  4907.6 2011.41
  4928.4 2001.68  4936.6 1999.27  4957.5 1994.72  4992.9 1993.17  4997.7 1990.31
  4998.2 1989.81  5017.3 1990.31  5022.0 1992.82  5042.9 1991.60  5078.3 2001.20
  5113.6 2005.56  5149.6 2007.57  5207.3 2008.05  5257.2 2010.18  5286.4 2015.57
  5353.5 2031.65  5378.0 2037.66  5392.5 2039.79  5456.2 2045.34  5468.8 2045.66
#Mann=7,-1,0
  4604.4     0.1       0  4626.1    0.07       0  4815.0     0.1       0
  4997.7    0.05       0  5017.3     0.1       0  5353.5    0.07       0
  5456.2   0.035       0
Bank Sta=4997.7,5017.3
Exp/Cntr=0.3,0.1

Type RM Length L Ch R = 1,92,0,0,0
BEGIN DESCRIPTION:
Flat Rock Creek 2 0.1
END DESCRIPTION:
XS GIS Cut Line= 4
      1801046.14     13929031.67      1800969.76     13928797.32
      1800759.69     13928568.16      1800643.34     13928436.18
#Sta/Elev= 30
  4687.8 2048.82  4735.8 2044.41  4797.4 2030.01  4894.7 2007.31  4905.8 2000.42
  4953.3 1991.96  4974.8 1991.32  4986.0 1988.70  4986.5 1988.20  5005.6 1988.70
  5024.2 1991.70  5066.7 1992.94  5073.5 1996.24  5095.1 1997.38  5101.9 2000.51
  5109.3 1999.34  5116.0 2002.57  5123.4 2000.96  5130.2 2003.85  5137.6 2002.30
  5144.4 2005.40  5151.8 2003.71  5158.6 2005.40  5173.0 2004.20  5208.5 2000.36
  5215.3 2002.43  5229.5 2002.48  5335.7 2032.35  5370.8 2038.61  5421.1 2043.55
#Mann=5,-1,0
  4687.8    0.07       0  4797.4     0.1       0  4986.0    0.05       0
  5005.6     0.1       0  5173.0    0.07       0
Bank Sta=4986,5005.6
Exp/Cntr=0.3,0.1

Chan Stop Cuts=-1