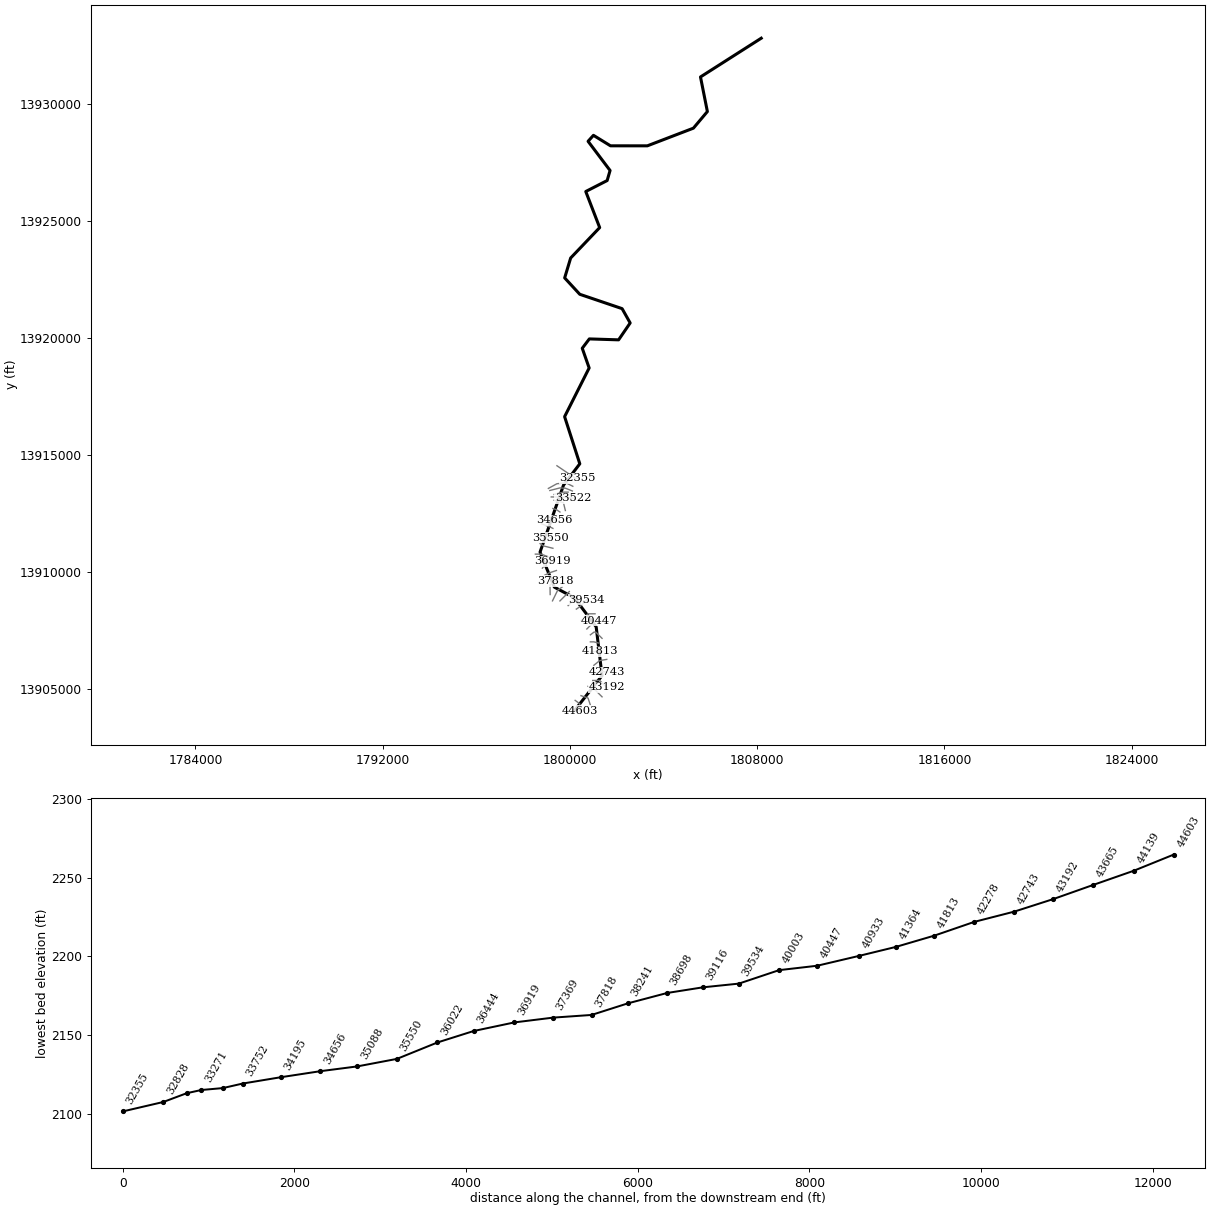
--- Flat Rock Creek.prj (project) ---

Proj Title=Flat Rock Creek Base Level Engineering
Current Plan=p01
Default Exp/Contr=0.3,0.1
English Units
Geom File=g01
Flow File=f01
Plan File=p01
BEGIN DESCRIPTION:
Flat Rock Creek
END DESCRIPTION:

--- Flat Rock Creek.p01 (plan) ---

Plan Title=Multiple Run
Short Identifier=Multiple
Geom File=g01
Flow File=f01
Subcritical Flow
K Sum by GR= 0
Std Step Tol= 0.01
Critical Tol= 0.01
Num of Std Step Trials= 20
Max Error Tol= 0.3
Flow Tol Ratio= 0.001
Split Flow NTrial= 30
Split Flow Tol= 0.02
Split Flow Ratio= 0.02
Log Output Level= 0
Friction Slope Method= 1
Unsteady Friction Slope Method= 2
Unsteady Bridges Friction Slope Method= 1
Parabolic Critical Depth
Global Vel Dist=  1 , 1 , 1
Global Log Level= 0
CheckData=True
Encroach Param= -1, 0, 0, 0
BEGIN DESCRIPTION:
Multiple Run
END DESCRIPTION:

--- Flat Rock Creek.f01 (steady flow) ---

Flow Title=Multiple
Number of Profiles=7
Profile Names=10-year,25-year,50-year,1pct_min,100-year,1pct_plu,500-year
River Rch & RM= Flat Rock Creek,Reach-1,44603
     377     603     805     522    1041    2078    1717
River Rch & RM= Flat Rock Creek,Reach-1,41364
    1039    1774    2473    1664    3321    6626    5926
River Rch & RM= Flat Rock Creek,Reach-1,36444
    1451    2523    3557    2419    4827    9631    8797
River Rch & RM= Flat Rock Creek,Reach-1,32355
    3209    5747    8262    5709   11392   22730   21454
River Rch & RM= Flat Rock Creek,Reach-1,23669
    4374    7928   11492    8000   15962   31848   30504
River Rch & RM= Flat Rock Creek,Reach-1,18151
    4612    8364   12127    8442   16843   33607   32188
River Rch & RM= Flat Rock Creek,Reach-1,10989
    7294   13410   19626   13775   27485   54839   53379
River Rch & RM= Flat Rock Creek,Reach-1,8694
    7346   13497   19745   13851   27637   55142   53616
River Rch & RM= Flat Rock Creek,Reach-1,4869
    7564   13905   20350   14280   28492   56848   55310
River Rch & RM= Flat Rock Creek,Reach-1,1639
    7597   13969   20446   14348   28629   57122   55587
Boundary for River Rch & Prof#=Flat Rock Creek,Reach-1,1
Up Type=0
Dn Type=3
Dn Slope=0.005
Boundary for River Rch & Prof#=Flat Rock Creek,Reach-1,2
Up Type=0
Dn Type=3
Dn Slope=0.005
Boundary for River Rch & Prof#=Flat Rock Creek,Reach-1,3
Up Type=0
Dn Type=3
Dn Slope=0.005
Boundary for River Rch & Prof#=Flat Rock Creek,Reach-1,4
Up Type=0
Dn Type=3
Dn Slope=0.005
Boundary for River Rch & Prof#=Flat Rock Creek,Reach-1,5
Up Type=0
Dn Type=3
Dn Slope=0.005
Boundary for River Rch & Prof#=Flat Rock Creek,Reach-1,6
Up Type=0
Dn Type=3
Dn Slope=0.005
Boundary for River Rch & Prof#=Flat Rock Creek,Reach-1,7
Up Type=0
Dn Type=3
Dn Slope=0.005

--- Flat Rock Creek.g01 (geometry) ---

Geom Title=Existing Conditions

River Reach=Flat Rock Creek,Reach-1
Reach XY= 30
      1800225.00     13904125.00      1801372.63     13905580.53
      1801123.63     13907665.33      1800195.13     13908905.23
      1799335.52     13909365.21      1798725.17     13910860.88
      1799728.53     13913723.55      1800423.78     13914635.51
      1799774.70     13916650.12      1800823.39     13918731.04
      1800528.67     13919573.42      1800830.67     13919973.02
      1802081.77     13919933.44      1802575.61     13920654.96
      1802231.07     13921266.87      1800422.70     13921880.83
      1799777.22     13922580.92      1800033.14     13923431.06
      1801273.18     13924731.12      1800678.61     13926273.50
      1801592.13     13926741.45      1801717.12     13927171.78
      1800777.24     13928419.07      1801006.80     13928674.88
      1801735.51     13928226.22      1803309.78     13928225.49
      1805277.43     13928980.52      1805874.48     13929690.22
      1805580.26     13931169.53      1808175.00     13932825.00

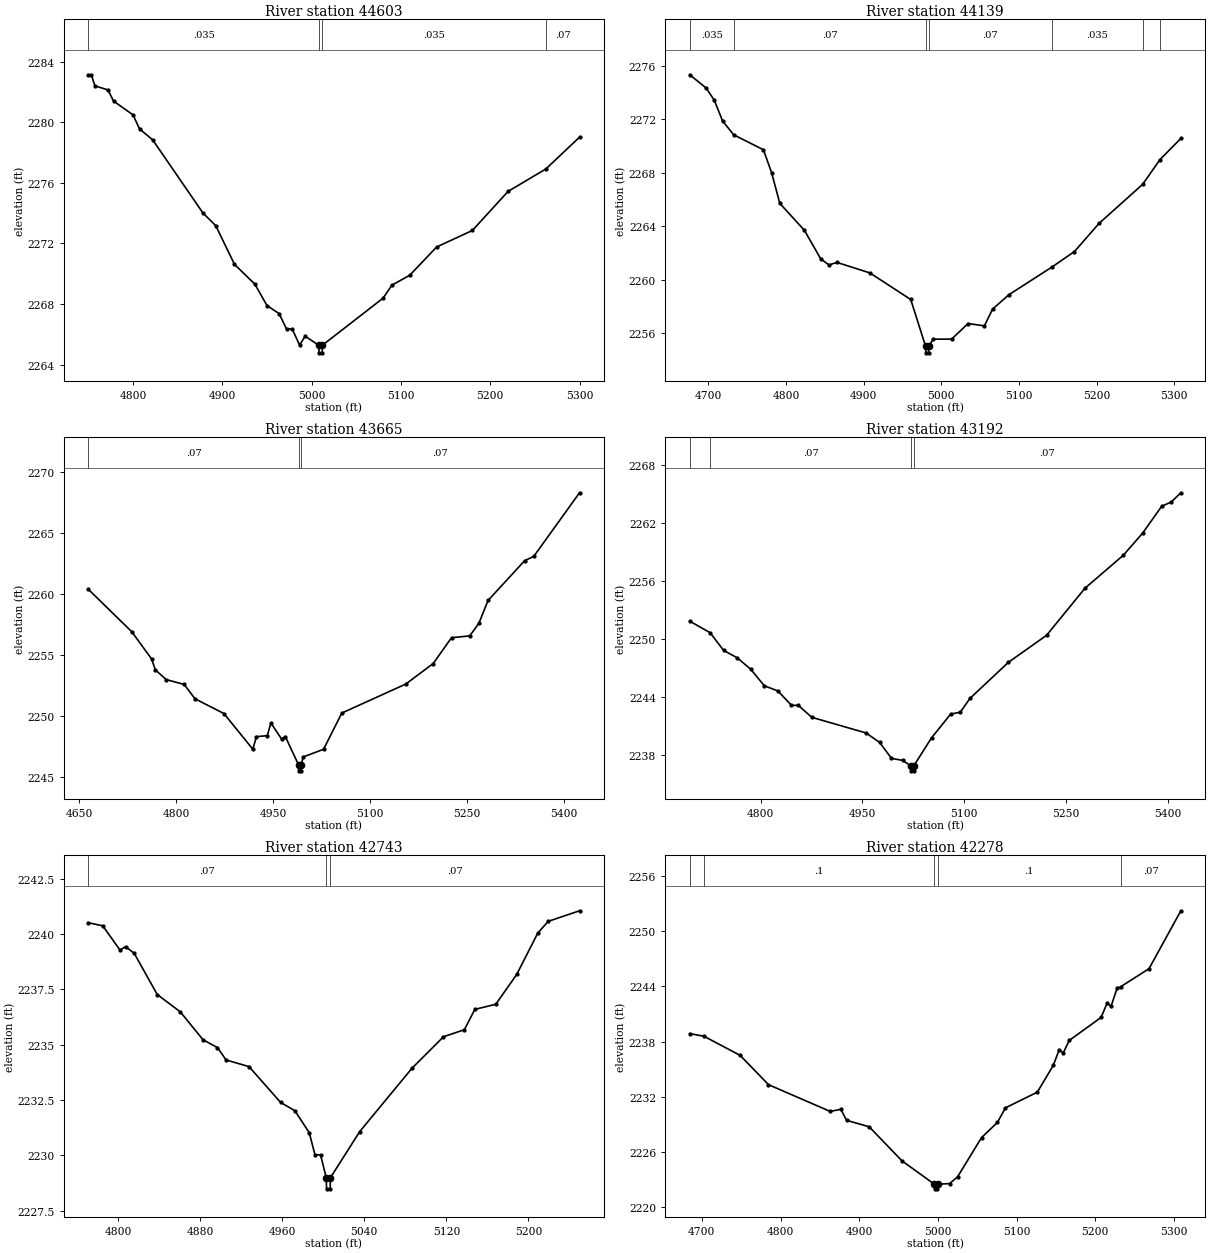
Type RM Length L Ch R = 1,44603,464,464,464
BEGIN DESCRIPTION:
Flat Rock Creek 90.0
END DESCRIPTION:
XS GIS Cut Line= 3
      1800224.98     13904525.02      1800425.00     13904375.00
      1800425.00     13904075.03
#Sta/Elev= 30
  4750.0 2283.13  4753.2 2283.13  4757.3 2282.40  4771.9 2282.13  4778.2 2281.39
  4800.0 2280.48  4807.3 2279.55  4821.9 2278.84  4878.2 2274.01  4892.7 2273.16
  4913.6 2270.61  4936.5 2269.30  4950.0 2267.89  4963.6 2267.36  4971.9 2266.34
  4978.2 2266.35  4986.5 2265.28  4992.7 2265.87  5008.0 2265.27  5008.3 2264.77
  5011.8 2264.77  5012.0 2265.27  5080.0 2268.38  5090.0 2269.24  5110.0 2269.90
  5140.0 2271.76  5180.0 2272.85  5220.0 2275.43  5262.3 2276.91  5300.0 2279.01
#Mann=4,-1,0
  4750.0   0.035       0  5008.0   0.035       0  5012.0   0.035       0
  5262.3    0.07       0
Bank Sta=5008,5012
Exp/Cntr=0.3,0.1

Type RM Length L Ch R = 1,44139,474,474,474
BEGIN DESCRIPTION:
Flat Rock Creek 89.0
END DESCRIPTION:
XS GIS Cut Line= 3
      1800474.97     13904725.01      1800775.00     13904625.00
      1800875.00     13904324.99
#Sta/Elev= 30
  4676.0 2275.32  4697.1 2274.33  4707.7 2273.41  4718.2 2271.87  4732.6 2270.83
  4770.9 2269.71  4781.4 2268.00  4792.0 2265.70  4823.6 2263.69  4844.7 2261.55
  4855.2 2261.10  4865.8 2261.28  4907.9 2260.50  4960.6 2258.51  4979.7 2255.02
  4980.0 2254.52  4983.5 2254.52  4983.7 2255.02  4989.6 2255.54  5013.3 2255.55
  5034.4 2256.71  5055.5 2256.54  5066.0 2257.79  5087.1 2258.87  5142.3 2260.93
  5171.5 2262.10  5203.1 2264.20  5259.2 2267.12  5281.7 2268.98  5308.5 2270.56
#Mann=7,-1,0
  4676.0   0.035       0  4732.6    0.07       0  4979.7    0.05       0
  4983.7    0.07       0  5142.3   0.035       0  5259.2    0.07       0
  5281.7   0.035       0
Bank Sta=4979.7,4983.7
Exp/Cntr=0.3,0.1

Type RM Length L Ch R = 1,43665,473,473,473
BEGIN DESCRIPTION:
Flat Rock Creek 88.0
END DESCRIPTION:
XS GIS Cut Line= 3
      1800775.02     13905124.99      1801075.00     13904975.00
      1801375.04     13904674.96
#Sta/Elev= 30
  4664.4 2260.39  4731.5 2256.91  4762.2 2254.67  4767.8 2253.79  4784.6 2252.98
  4812.5 2252.58  4829.3 2251.40  4874.0 2250.19  4918.7 2247.26  4924.3 2248.29
  4941.1 2248.37  4946.7 2249.41  4963.4 2248.08  4969.0 2248.30  4989.4 2245.98
  4989.7 2245.48  4993.2 2245.48  4993.4 2245.98  4997.0 2246.63  5028.1 2247.25
  5056.4 2250.23  5155.3 2252.61  5197.8 2254.30  5226.1 2256.42  5254.3 2256.57
  5268.5 2257.61  5282.6 2259.48  5339.2 2262.75  5353.3 2263.10  5424.1 2268.33
#Mann=3,-1,0
  4664.4    0.07       0  4989.4    0.05       0  4993.4    0.07       0
Bank Sta=4989.4,4993.4
Exp/Cntr=0.3,0.1

Type RM Length L Ch R = 1,43192,449,449,449
BEGIN DESCRIPTION:
Flat Rock Creek 87.0
END DESCRIPTION:
XS GIS Cut Line= 3
      1800975.04     13905375.00      1801275.00     13905375.00
      1801574.98     13905075.02
#Sta/Elev= 30
  4695.5 2251.84  4725.5 2250.65  4745.5 2248.81  4765.5 2248.05  4785.5 2246.86
  4805.5 2245.15  4825.5 2244.62  4845.5 2243.13  4855.5 2243.13  4875.5 2241.89
  4955.5 2240.27  4975.5 2239.29  4993.0 2237.64  5009.6 2237.43  5021.7 2236.85
  5022.0 2236.35  5025.5 2236.35  5025.7 2236.85  5052.0 2239.76  5080.3 2242.23
  5094.5 2242.42  5108.6 2243.84  5165.2 2247.57  5221.7 2250.38  5278.3 2255.25
  5334.9 2258.67  5363.2 2260.94  5391.4 2263.73  5405.6 2264.18  5419.7 2265.13
#Mann=4,-1,0
  4695.5   0.035       0  4725.5    0.07       0  5021.7    0.05       0
  5025.7    0.07       0
Bank Sta=5021.7,5025.7
Exp/Cntr=0.3,0.1

Type RM Length L Ch R = 1,42743,465,465,465
BEGIN DESCRIPTION:
Flat Rock Creek 86.0
END DESCRIPTION:
XS GIS Cut Line= 3
      1801124.99     13905675.00      1801325.00     13905775.00
      1801575.03     13905724.99
#Sta/Elev= 30
  4771.2 2240.52  4785.2 2240.38  4802.0 2239.28  4807.5 2239.44  4815.9 2239.13
  4838.3 2237.27  4860.7 2236.49  4883.0 2235.22  4897.0 2234.87  4905.4 2234.31
  4927.7 2234.01  4958.5 2232.39  4972.5 2232.01  4986.4 2231.02  4992.0 2230.02
  4997.4 2230.02  5003.0 2228.98  5003.3 2228.48  5006.8 2228.48  5007.0 2228.98
  5035.6 2231.07  5086.6 2233.94  5117.2 2235.36  5137.6 2235.68  5147.8 2236.60
  5168.2 2236.83  5188.6 2238.18  5209.0 2240.04  5219.2 2240.58  5249.8 2241.06
#Mann=3,-1,0
  4771.2    0.07       0  5003.0    0.05       0  5007.0    0.07       0
Bank Sta=5003,5007
Exp/Cntr=0.3,0.1

Type RM Length L Ch R = 1,42278,465,465,465
BEGIN DESCRIPTION:
Flat Rock Creek 85.0
END DESCRIPTION:
XS GIS Cut Line= 3
      1801024.99     13906024.99      1801275.00     13906225.00
      1801574.99     13906275.00
#Sta/Elev= 30
  4684.6 2238.86  4702.5 2238.58  4748.6 2236.50  4784.7 2233.31  4863.1 2230.40
  4876.7 2230.63  4883.9 2229.43  4912.7 2228.73  4954.3 2225.03  4995.6 2222.48
  4995.8 2221.98  4999.3 2221.98  4999.6 2222.48  5014.9 2222.55  5025.0 2223.28
  5055.5 2227.55  5075.7 2229.20  5085.9 2230.79  5126.4 2232.49  5146.7 2235.40
  5154.3 2237.12  5159.4 2236.75  5167.0 2238.12  5207.5 2240.62  5215.1 2242.17
  5220.2 2241.84  5227.8 2243.79  5232.2 2243.95  5268.4 2245.92  5308.9 2252.22
#Mann=5,-1,0
  4684.6    0.07       0  4702.5     0.1       0  4995.6    0.05       0
  4999.6     0.1       0  5232.2    0.07       0
Bank Sta=4995.6,4999.6
Exp/Cntr=0.3,0.1

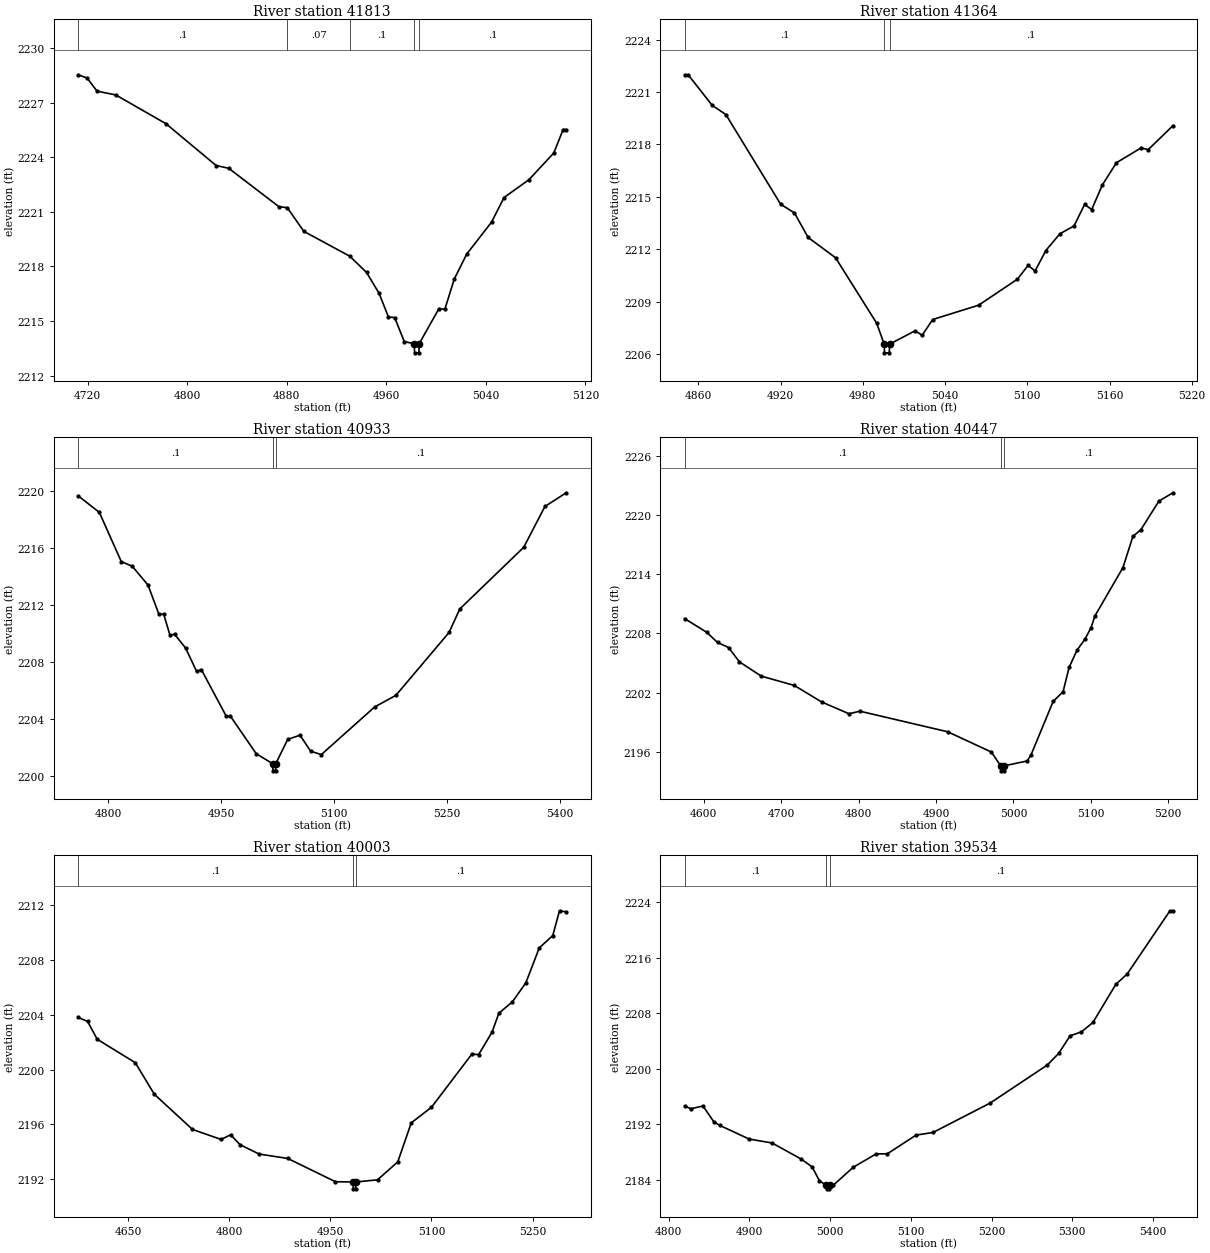
Type RM Length L Ch R = 1,41813,449,449,449
BEGIN DESCRIPTION:
Flat Rock Creek 84.0
END DESCRIPTION:
XS GIS Cut Line= 3
      1800884.96     13906588.84      1801175.00     13906625.00
      1801275.01     13906625.00
#Sta/Elev= 30
  4712.3 2228.54  4719.5 2228.36  4727.5 2227.64  4742.6 2227.43  4782.9 2225.85
  4823.2 2223.55  4833.3 2223.40  4873.6 2221.29  4880.4 2221.23  4893.7 2219.93
  4930.7 2218.56  4944.1 2217.67  4954.2 2216.52  4961.7 2215.22  4966.7 2215.19
  4974.4 2213.87  4982.4 2213.75  4982.7 2213.25  4986.2 2213.25  4986.4 2213.75
  5002.1 2215.66  5007.1 2215.66  5014.6 2217.31  5024.6 2218.68  5044.6 2220.44
  5054.6 2221.79  5074.6 2222.77  5094.6 2224.24  5102.1 2225.53  5104.6 2225.53
#Mann=5,-1,0
  4712.3     0.1       0  4880.4    0.07       0  4930.7     0.1       0
  4982.4    0.05       0  4986.4     0.1       0
Bank Sta=4982.4,4986.4
Exp/Cntr=0.3,0.1

Type RM Length L Ch R = 1,41364,431,431,431
BEGIN DESCRIPTION:
Flat Rock Creek 83.0
END DESCRIPTION:
XS GIS Cut Line= 3
      1800875.02     13907025.00      1801025.00     13907025.00
      1801224.97     13906975.01
#Sta/Elev= 30
  4850.1 2221.99  4852.6 2221.99  4870.1 2220.24  4880.1 2219.71  4920.1 2214.57
  4930.1 2214.08  4940.1 2212.67  4960.1 2211.51  4990.1 2207.76  4995.6 2206.56
  4995.8 2206.06  4999.3 2206.06  4999.6 2206.56  5018.1 2207.32  5023.3 2207.07
  5031.0 2207.97  5064.5 2208.79  5092.8 2210.28  5100.6 2211.07  5105.7 2210.75
  5113.5 2211.92  5123.8 2212.88  5134.1 2213.33  5141.8 2214.56  5147.0 2214.27
  5154.7 2215.67  5165.0 2216.95  5183.0 2217.80  5188.2 2217.70  5206.2 2219.07
#Mann=3,-1,0
  4850.1     0.1       0  4995.6    0.05       0  4999.6     0.1       0
Bank Sta=4995.6,4999.6
Exp/Cntr=0.3,0.1

Type RM Length L Ch R = 1,40933,486,486,486
BEGIN DESCRIPTION:
Flat Rock Creek 82.0
END DESCRIPTION:
XS GIS Cut Line= 4
      1800874.97     13907324.97      1801034.67     13907444.75
      1801115.38     13907434.62      1801374.98     13907175.02
#Sta/Elev= 30
  4760.1 2219.64  4788.3 2218.47  4817.4 2215.02  4832.0 2214.69  4852.9 2213.37
  4867.4 2211.31  4873.7 2211.33  4882.0 2209.86  4888.3 2209.91  4902.9 2208.94
  4917.4 2207.31  4923.7 2207.44  4956.8 2204.16  4962.4 2204.16  4996.6 2201.53
  5018.5 2200.83  5018.8 2200.33  5022.3 2200.33  5022.5 2200.83  5038.4 2202.54
  5054.7 2202.83  5068.8 2201.71  5083.0 2201.47  5153.7 2204.81  5182.0 2205.63
  5252.7 2210.05  5266.8 2211.69  5351.7 2216.02  5379.9 2218.89  5408.2 2219.85
#Mann=3,-1,0
  4760.1     0.1       0  5018.5    0.05       0  5022.5     0.1       0
Bank Sta=5018.5,5022.5
Exp/Cntr=0.3,0.1

Type RM Length L Ch R = 1,40447,444,444,444
BEGIN DESCRIPTION:
Flat Rock Creek 81.0
END DESCRIPTION:
XS GIS Cut Line= 3
      1800725.03     13907575.03      1801025.00     13907875.00
      1801225.03     13907925.01
#Sta/Elev= 30
  4575.5 2209.50  4603.7 2208.13  4617.9 2207.09  4632.0 2206.58  4646.2 2205.12
  4674.4 2203.68  4716.9 2202.74  4752.2 2201.07  4787.6 2199.87  4801.7 2200.13
  4914.9 2198.05  4971.4 2196.00  4983.6 2194.59  4983.8 2194.09  4987.3 2194.09
  4987.6 2194.59  5017.8 2195.09  5022.9 2195.74  5051.3 2201.12  5064.1 2202.10
  5071.9 2204.57  5082.2 2206.32  5092.5 2207.44  5100.2 2208.59  5105.4 2209.80
  5141.4 2214.67  5154.3 2217.83  5164.6 2218.51  5187.8 2221.40  5205.9 2222.25
#Mann=3,-1,0
  4575.5     0.1       0  4983.6    0.05       0  4987.6     0.1       0
Bank Sta=4983.6,4987.6
Exp/Cntr=0.3,0.1

Type RM Length L Ch R = 1,40003,469,469,469
BEGIN DESCRIPTION:
Flat Rock Creek 80.0
END DESCRIPTION:
XS GIS Cut Line= 3
      1800475.01     13907925.01      1800775.00     13908225.00
      1801075.05     13908225.00
#Sta/Elev= 30
  4575.7 2203.82  4589.8 2203.52  4604.0 2202.22  4660.5 2200.51  4688.8 2198.20
  4745.4 2195.63  4787.8 2194.90  4802.0 2195.24  4816.1 2194.51  4844.4 2193.83
  4886.8 2193.51  4957.5 2191.81  4983.8 2191.79  4984.1 2191.29  4987.6 2191.29
  4987.8 2191.79  5020.0 2191.95  5050.0 2193.26  5070.0 2196.11  5100.0 2197.25
  5160.0 2201.14  5170.0 2201.10  5190.0 2202.75  5200.0 2204.12  5220.0 2204.95
  5240.0 2206.34  5260.0 2208.90  5280.0 2209.80  5290.0 2211.61  5300.0 2211.53
#Mann=3,-1,0
  4575.7     0.1       0  4983.8    0.05       0  4987.8     0.1       0
Bank Sta=4983.8,4987.8
Exp/Cntr=0.3,0.1

Type RM Length L Ch R = 1,39534,418,418,418
BEGIN DESCRIPTION:
Flat Rock Creek 79.0
END DESCRIPTION:
XS GIS Cut Line= 3
      1800274.97     13908424.98      1800425.00     13908525.00
      1800725.02     13908825.02
#Sta/Elev= 30
  4819.9 2194.64  4827.4 2194.26  4842.5 2194.66  4856.0 2192.36  4863.5 2191.85
  4899.6 2189.90  4928.1 2189.33  4964.2 2187.01  4977.7 2185.89  4986.7 2183.90
  4995.2 2183.23  4995.5 2182.73  4999.0 2182.73  4999.2 2183.23  5003.7 2183.23
  5028.5 2185.83  5056.8 2187.75  5070.9 2187.78  5106.3 2190.46  5127.5 2190.85
  5198.2 2195.08  5268.9 2200.55  5283.1 2202.23  5297.2 2204.76  5311.3 2205.33
  5325.5 2206.68  5353.8 2212.16  5367.9 2213.66  5420.9 2222.76  5424.5 2222.76
#Mann=3,-1,0
  4819.9     0.1       0  4995.2    0.05       0  4999.2     0.1       0
Bank Sta=4995.2,4999.2
Exp/Cntr=0.3,0.1

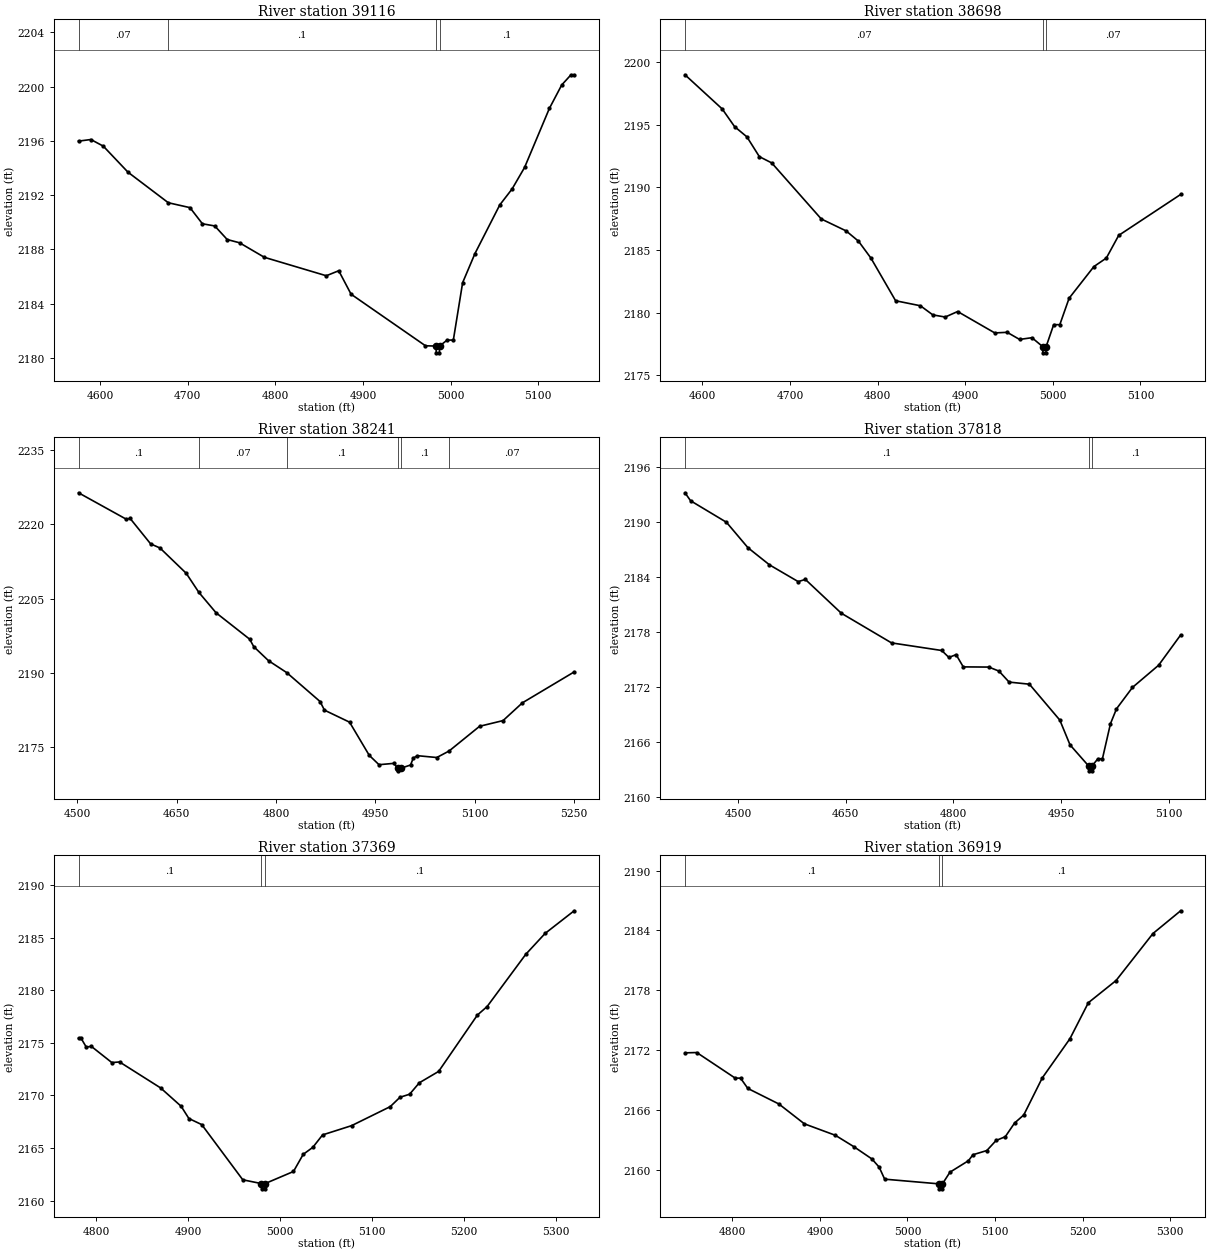
Type RM Length L Ch R = 1,39116,418,418,418
BEGIN DESCRIPTION:
Flat Rock Creek 78.0
END DESCRIPTION:
XS GIS Cut Line= 3
      1799925.02     13908575.02      1800225.00     13908875.00
      1800325.03     13908975.03
#Sta/Elev= 30
  4575.3 2195.98  4589.4 2196.10  4603.6 2195.61  4631.8 2193.69  4677.8 2191.44
  4702.5 2191.08  4716.7 2189.89  4730.8 2189.73  4745.0 2188.73  4759.1 2188.49
  4787.4 2187.42  4858.1 2186.06  4872.3 2186.43  4886.4 2184.70  4971.3 2180.90
  4983.4 2180.88  4983.6 2180.38  4987.1 2180.38  4987.4 2180.88  4996.0 2181.32
  5003.1 2181.32  5013.7 2185.55  5027.8 2187.70  5056.1 2191.28  5070.2 2192.46
  5084.4 2194.04  5112.7 2198.39  5126.8 2200.12  5137.4 2200.87  5141.0 2200.87
#Mann=4,-1,0
  4575.3    0.07       0  4677.8     0.1       0  4983.4    0.05       0
  4987.4     0.1       0
Bank Sta=4983.4,4987.4
Exp/Cntr=0.3,0.1

Type RM Length L Ch R = 1,38698,457,457,457
BEGIN DESCRIPTION:
Flat Rock Creek 77.0
END DESCRIPTION:
XS GIS Cut Line= 3
      1799574.98     13908774.98      1799875.00     13909075.00
      1799974.99     13909174.99
#Sta/Elev= 30
  4580.2 2198.99  4622.7 2196.26  4636.8 2194.85  4650.9 2194.03  4665.1 2192.45
  4679.2 2191.95  4735.8 2187.47  4764.1 2186.52  4778.2 2185.70  4792.4 2184.35
  4820.6 2180.94  4848.9 2180.54  4863.1 2179.81  4877.2 2179.64  4891.4 2180.08
  4933.8 2178.37  4947.9 2178.42  4962.1 2177.85  4976.2 2177.99  4988.4 2177.28
  4988.6 2176.78  4992.1 2176.78  4992.4 2177.28  5001.0 2179.03  5008.0 2179.03
  5018.6 2181.14  5046.9 2183.67  5061.1 2184.35  5075.2 2186.16  5145.9 2189.43
#Mann=3,-1,0
  4580.2    0.07       0  4988.4    0.05       0  4992.4    0.07       0
Bank Sta=4988.4,4992.4
Exp/Cntr=0.3,0.1

Type RM Length L Ch R = 1,38241,423,423,423
BEGIN DESCRIPTION:
Flat Rock Creek 76.0
END DESCRIPTION:
XS GIS Cut Line= 3
      1799257.42     13908777.15      1799475.00     13909225.00
      1799674.99     13909374.99
#Sta/Elev= 30
  4502.1 2226.36  4574.3 2221.01  4579.9 2221.19  4610.9 2216.04  4625.0 2215.21
  4664.6 2210.10  4683.7 2206.24  4709.7 2202.11  4760.4 2196.78  4766.5 2195.28
  4788.8 2192.44  4816.3 2190.03  4866.6 2184.19  4873.2 2182.45  4911.1 2180.02
  4940.8 2173.32  4955.5 2171.43  4977.8 2171.70  4984.0 2170.69  4984.2 2170.19
  4988.0 2170.69  5003.1 2171.37  5007.3 2172.78  5013.6 2173.25  5042.7 2172.88
  5061.2 2174.19  5107.3 2179.19  5142.7 2180.34  5171.9 2183.93  5250.0 2190.17
#Mann=6,-1,0
  4502.1     0.1       0  4683.7    0.07       0  4816.3     0.1       0
  4984.0    0.05       0  4988.0     0.1       0  5061.2    0.07       0
Bank Sta=4984,4988
Exp/Cntr=0.3,0.1

Type RM Length L Ch R = 1,37818,449,449,449
BEGIN DESCRIPTION:
Flat Rock Creek 75.0
END DESCRIPTION:
XS GIS Cut Line= 4
      1799157.19     13909047.17      1799151.33     13909451.33
      1799275.00     13909575.00      1799375.00     13909625.00
#Sta/Elev= 30
  4425.9 2193.18  4433.7 2192.31  4483.7 2189.96  4513.7 2187.18  4543.7 2185.31
  4583.7 2183.48  4593.7 2183.72  4643.8 2180.03  4713.8 2176.79  4783.8 2175.96
  4793.8 2175.20  4803.8 2175.51  4813.8 2174.17  4849.4 2174.15  4863.6 2173.71
  4877.7 2172.51  4906.0 2172.28  4948.4 2168.36  4962.6 2165.66  4988.9 2163.32
  4989.1 2162.82  4992.6 2162.82  4992.9 2163.32  5001.5 2164.14  5007.8 2164.14
  5019.0 2167.97  5027.4 2169.59  5049.7 2171.93  5086.1 2174.35  5116.8 2177.65
#Mann=3,-1,0
  4425.9     0.1       0  4988.9    0.05       0  4992.9     0.1       0
Bank Sta=4988.9,4992.9
Exp/Cntr=0.3,0.1

Type RM Length L Ch R = 1,37369,450,450,450
BEGIN DESCRIPTION:
Flat Rock Creek 74.0
END DESCRIPTION:
XS GIS Cut Line= 3
      1798925.01     13909875.01      1799125.00     13909975.00
      1799424.98     13910074.99
#Sta/Elev= 30
  4780.5 2175.44  4783.3 2175.44  4788.9 2174.61  4794.5 2174.67  4816.8 2173.13
  4825.2 2173.19  4869.9 2170.72  4892.3 2168.97  4900.7 2167.81  4914.7 2167.23
  4959.4 2161.98  4979.7 2161.62  4980.0 2161.12  4983.5 2161.12  4983.7 2161.62
  5014.6 2162.77  5025.2 2164.40  5035.7 2165.07  5046.3 2166.25  5077.9 2167.13
  5120.0 2168.94  5130.6 2169.83  5141.1 2170.12  5151.7 2171.21  5172.7 2172.29
  5214.9 2177.65  5225.5 2178.46  5267.6 2183.43  5288.7 2185.42  5320.3 2187.57
#Mann=3,-1,0
  4780.5     0.1       0  4979.7    0.05       0  4983.7     0.1       0
Bank Sta=4979.7,4983.7
Exp/Cntr=0.3,0.1

Type RM Length L Ch R = 1,36919,475,475,475
BEGIN DESCRIPTION:
Flat Rock Creek 73.0
END DESCRIPTION:
XS GIS Cut Line= 3
      1798825.02     13910175.03      1798975.00     13910375.00
      1799275.00     13910475.00
#Sta/Elev= 30
  4745.9 2171.72  4759.4 2171.75  4803.2 2169.19  4809.4 2169.18  4817.7 2168.15
  4853.2 2166.59  4882.3 2164.60  4917.7 2163.45  4938.6 2162.32  4959.4 2161.08
  4967.7 2160.26  4974.0 2159.05  5036.0 2158.58  5036.3 2158.08  5039.8 2158.08
  5040.0 2158.58  5048.6 2159.75  5069.7 2160.90  5074.9 2161.50  5090.7 2161.92
  5101.3 2162.93  5111.8 2163.31  5122.4 2164.68  5132.9 2165.49  5154.0 2169.20
  5185.6 2173.13  5206.7 2176.75  5238.3 2178.97  5280.5 2183.69  5312.1 2185.97
#Mann=3,-1,0
  4745.9     0.1       0  5036.0    0.05       0  5040.0     0.1       0
Bank Sta=5036,5040
Exp/Cntr=0.3,0.1

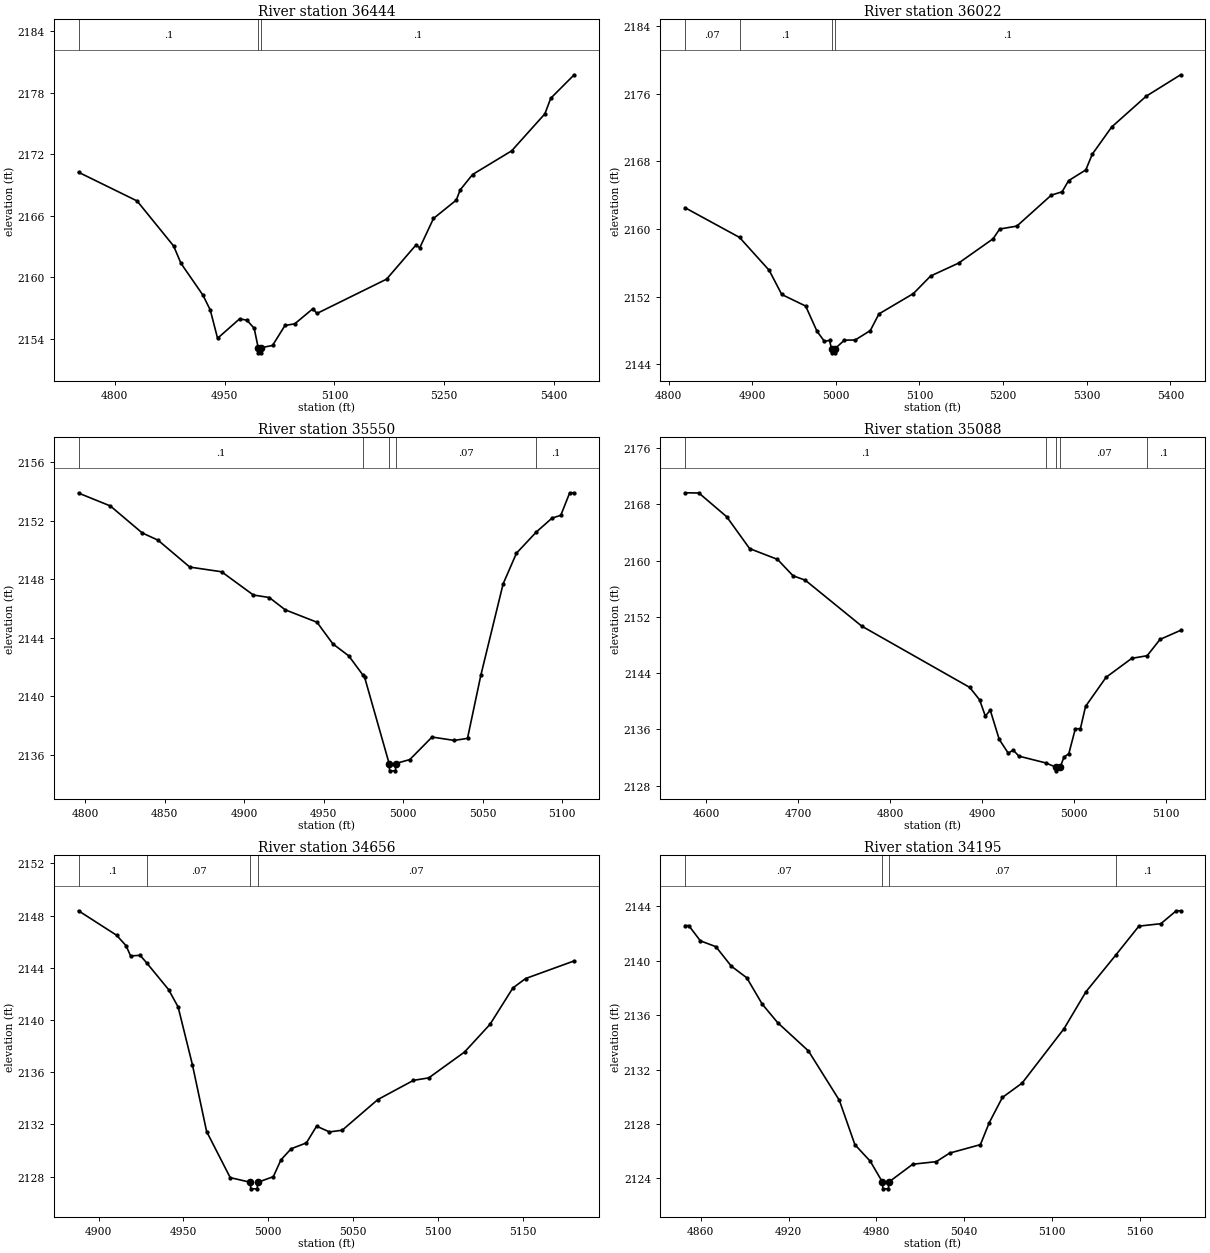
Type RM Length L Ch R = 1,36444,422,422,422
BEGIN DESCRIPTION:
Flat Rock Creek 72.0
END DESCRIPTION:
XS GIS Cut Line= 3
      1798524.99     13910775.00      1798775.00     13910775.00
      1799174.99     13910625.00
#Sta/Elev= 30
  4750.4 2170.23  4830.4 2167.43  4880.4 2163.03  4890.4 2161.34  4920.4 2158.24
  4930.4 2156.79  4940.4 2154.03  4970.4 2155.92  4980.4 2155.80  4990.4 2155.01
  4995.9 2153.11  4996.2 2152.61  4999.7 2152.61  4999.9 2153.11  5015.5 2153.33
  5032.5 2155.28  5045.8 2155.44  5070.7 2156.92  5076.1 2156.45  5171.3 2159.80
  5211.3 2163.12  5216.7 2162.87  5235.4 2165.72  5266.5 2167.51  5271.9 2168.51
  5288.8 2170.01  5342.2 2172.32  5387.6 2175.93  5395.6 2177.45  5427.6 2179.74
#Mann=3,-1,0
  4750.4     0.1       0  4995.9    0.05       0  4999.9     0.1       0
Bank Sta=4995.9,4999.9
Exp/Cntr=0.3,0.1

Type RM Length L Ch R = 1,36022,472,472,472
BEGIN DESCRIPTION:
Flat Rock Creek 71.0
END DESCRIPTION:
XS GIS Cut Line= 3
      1798724.96     13911225.02      1798875.00     13911125.00
      1799274.97     13911025.01
#Sta/Elev= 30
  4819.7 2162.52  4884.9 2159.00  4920.4 2155.10  4935.4 2152.24  4964.0 2150.87
  4977.5 2147.89  4986.5 2146.68  4992.5 2146.81  4994.9 2145.83  4995.2 2145.33
  4998.8 2145.33  4999.1 2145.83  5010.3 2146.83  5023.2 2146.85  5041.3 2147.97
  5051.6 2149.94  5092.8 2152.35  5113.4 2154.43  5146.9 2155.96  5188.1 2158.84
  5195.9 2159.99  5216.5 2160.34  5257.7 2164.01  5270.6 2164.40  5278.3 2165.72
  5298.9 2166.99  5306.7 2168.86  5329.9 2172.08  5371.1 2175.72  5412.3 2178.26
#Mann=4,-1,0
  4819.7    0.07       0  4884.9     0.1       0  4994.9    0.05       0
  4999.1     0.1       0
Bank Sta=4994.9,4999.1
Exp/Cntr=0.3,0.1

Type RM Length L Ch R = 1,35550,462,462,462
BEGIN DESCRIPTION:
Flat Rock Creek 70.0
END DESCRIPTION:
XS GIS Cut Line= 3
      1798874.97     13911525.00      1799075.00     13911525.00
      1799174.97     13911475.01
#Sta/Elev= 30
  4795.8 2153.89  4815.8 2153.01  4835.8 2151.17  4845.8 2150.67  4865.8 2148.83
  4885.8 2148.51  4905.8 2146.92  4915.8 2146.75  4925.8 2145.91  4945.8 2145.06
  4955.8 2143.58  4965.8 2142.76  4974.5 2141.48  4975.8 2141.29  4991.2 2135.40
  4991.5 2134.90  4995.2 2134.90  4995.4 2135.40  5004.2 2135.67  5018.2 2137.21
  5032.2 2136.98  5040.5 2137.12  5048.9 2141.44  5062.9 2147.68  5071.3 2149.78
  5083.9 2151.24  5093.7 2152.18  5099.2 2152.37  5104.8 2153.91  5107.6 2153.91
#Mann=5,-1,0
  4795.8     0.1       0  4974.5    0.07       0  4991.2    0.05       0
  4995.4    0.07       0  5083.9     0.1       0
Bank Sta=4991.2,4995.4
Exp/Cntr=0.3,0.1

Type RM Length L Ch R = 1,35088,432,432,432
BEGIN DESCRIPTION:
Flat Rock Creek 69.0
END DESCRIPTION:
XS GIS Cut Line= 3
      1798775.02     13912074.99      1799175.00     13911925.00
      1799275.01     13911874.99
#Sta/Elev= 30
  4576.8 2169.66  4591.9 2169.63  4622.2 2166.25  4647.1 2161.72  4677.4 2160.19
  4694.3 2157.86  4707.6 2157.23  4769.0 2150.70  4886.5 2141.98  4897.2 2140.21
  4903.4 2137.91  4908.8 2138.74  4918.5 2134.60  4928.3 2132.64  4933.7 2133.07
  4939.9 2132.21  4969.3 2131.24  4980.5 2130.62  4980.8 2130.12  4984.8 2130.62
  4988.9 2132.07  4994.2 2132.56  5001.3 2136.11  5006.8 2136.11  5012.4 2139.28
  5034.7 2143.42  5062.7 2146.12  5079.4 2146.49  5093.4 2148.81  5115.8 2150.10
#Mann=5,-1,0
  4576.8     0.1       0  4969.3    0.07       0  4980.5    0.05       0
  4984.8    0.07       0  5079.4     0.1       0
Bank Sta=4980.5,4984.8
Exp/Cntr=0.3,0.1

Type RM Length L Ch R = 1,34656,461,461,461
BEGIN DESCRIPTION:
Flat Rock Creek 68.0
END DESCRIPTION:
XS GIS Cut Line= 3
      1799075.00     13912375.00      1799175.00     13912325.00
      1799325.02     13912224.99
#Sta/Elev= 30
  4888.2 2148.37  4910.6 2146.50  4916.2 2145.70  4918.9 2144.91  4924.5 2144.96
  4928.3 2144.39  4941.3 2142.33  4946.9 2141.00  4955.3 2136.59  4963.7 2131.46
  4977.6 2127.93  4989.5 2127.57  4989.7 2127.07  4993.5 2127.07  4993.8 2127.57
  5003.0 2128.00  5007.5 2129.29  5013.5 2130.14  5022.5 2130.59  5028.5 2131.87
  5036.1 2131.43  5043.6 2131.56  5064.6 2133.91  5085.6 2135.38  5094.6 2135.57
  5115.7 2137.55  5130.7 2139.67  5144.2 2142.46  5151.7 2143.18  5180.3 2144.53
#Mann=4,-1,0
  4888.2     0.1       0  4928.3    0.07       0  4989.5    0.05       0
  4993.8    0.07       0
Bank Sta=4989.5,4993.8
Exp/Cntr=0.3,0.1

Type RM Length L Ch R = 1,34195,443,443,443
BEGIN DESCRIPTION:
Flat Rock Creek 67.0
END DESCRIPTION:
XS GIS Cut Line= 3
      1799274.99     13912725.00      1799425.00     13912675.00
      1799575.00     13912575.00
#Sta/Elev= 30
  4849.3 2142.59  4851.9 2142.59  4859.8 2141.47  4870.4 2141.04  4880.9 2139.61
  4891.5 2138.75  4902.0 2136.82  4912.6 2135.45  4933.6 2133.37  4954.7 2129.74
  4965.3 2126.48  4975.8 2125.26  4984.1 2123.73  4984.4 2123.23  4988.2 2123.23
  4988.5 2123.73  5004.8 2125.04  5020.9 2125.23  5030.0 2125.86  5051.0 2126.48
  5057.0 2128.09  5066.0 2129.95  5079.5 2131.01  5108.1 2135.01  5123.1 2137.73
  5143.4 2140.42  5159.2 2142.55  5174.2 2142.73  5184.7 2143.68  5187.7 2143.68
#Mann=4,-1,0
  4849.3    0.07       0  4984.1    0.05       0  4988.5    0.07       0
  5143.4     0.1       0
Bank Sta=4984.1,4988.5
Exp/Cntr=0.3,0.1

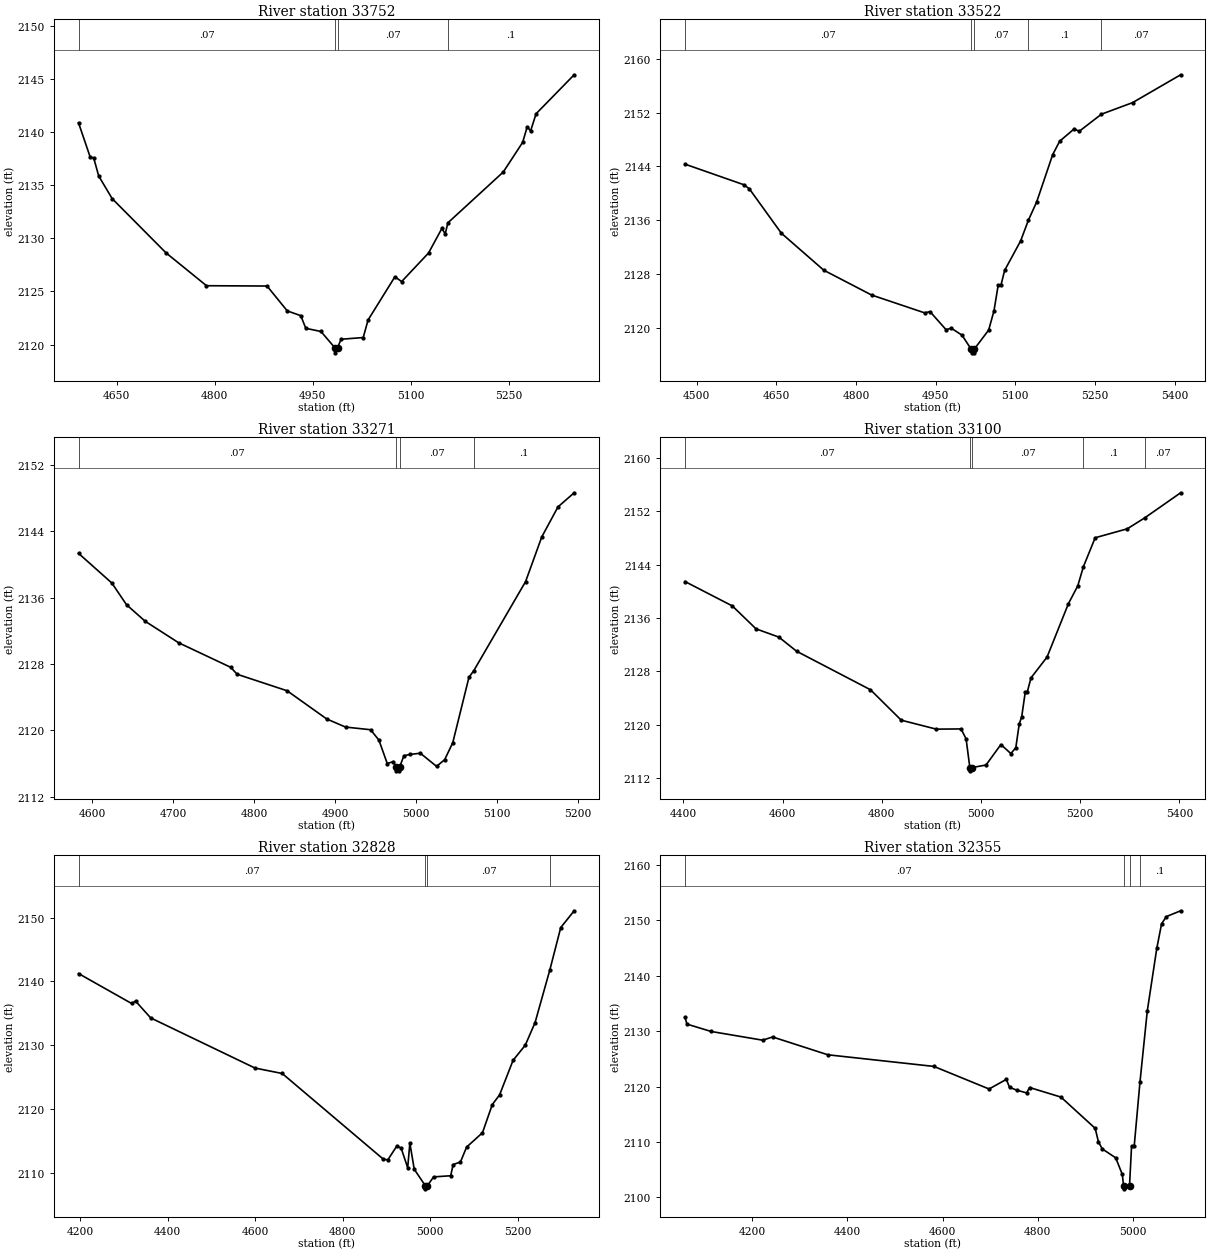
Type RM Length L Ch R = 1,33752,230,230,230
BEGIN DESCRIPTION:
Flat Rock Creek 66.0
END DESCRIPTION:
XS GIS Cut Line= 3
      1799324.99     13913075.00      1799725.00     13912975.00
      1799806.46     13912638.33
#Sta/Elev= 30
  4591.6 2140.88  4609.6 2137.63  4614.8 2137.58  4622.5 2135.87  4643.1 2133.74
  4725.6 2128.63  4787.5 2125.54  4880.2 2125.51  4911.1 2123.17  4931.8 2122.72
  4939.5 2121.53  4962.7 2121.23  4983.7 2119.72  4984.0 2119.22  4988.1 2119.72
  4993.6 2120.50  5027.4 2120.66  5034.8 2122.31  5075.9 2126.38  5086.2 2125.93
  5127.4 2128.62  5147.8 2130.93  5152.9 2130.42  5157.0 2131.46  5241.7 2136.24
  5271.4 2139.03  5278.4 2140.50  5283.6 2140.11  5292.0 2141.73  5350.3 2145.40
#Mann=4,-1,0
  4591.6    0.07       0  4983.7    0.05       0  4988.1    0.07       0
  5157.0     0.1       0
Bank Sta=4983.7,4988.1
Exp/Cntr=0.3,0.1

Type RM Length L Ch R = 1,33522,251,251,251
BEGIN DESCRIPTION:
Flat Rock Creek 65.1
END DESCRIPTION:
XS GIS Cut Line= 3
      1799203.66     13913219.02      1799645.85     13913213.55
      1800135.03     13913169.32
#Sta/Elev= 30
  4478.1 2144.35  4589.4 2141.28  4599.4 2140.68  4659.5 2134.11  4739.5 2128.61
  4829.5 2124.93  4929.5 2122.28  4939.5 2122.47  4969.7 2119.79  4979.7 2120.00
  4999.8 2118.97  5017.4 2116.85  5017.8 2116.35  5022.0 2116.35  5022.4 2116.85
  5050.0 2119.73  5060.0 2122.58  5067.9 2126.38  5073.0 2126.35  5080.1 2128.59
  5110.2 2132.96  5124.8 2136.03  5140.4 2138.74  5170.5 2145.75  5183.7 2147.75
  5210.7 2149.56  5220.7 2149.23  5262.3 2151.76  5321.1 2153.48  5411.5 2157.61
#Mann=5,-1,0
  4478.1    0.07       0  5017.4    0.05       0  5022.4    0.07       0
  5124.8     0.1       0  5262.3    0.07       0
Bank Sta=5017.4,5022.4
Exp/Cntr=0.3,0.1

Type RM Length L Ch R = 1,33271,171,171,171
BEGIN DESCRIPTION:
Flat Rock Creek 65.0
END DESCRIPTION:
XS GIS Cut Line= 3
      1799324.98     13913325.00      1799725.00     13913425.00
      1799924.97     13913425.00
#Sta/Elev= 30
  4583.1 2141.32  4624.3 2137.74  4642.4 2135.13  4665.6 2133.13  4706.8 2130.55
  4771.2 2127.59  4779.0 2126.76  4840.8 2124.77  4889.8 2121.37  4913.0 2120.40
  4943.9 2120.08  4954.2 2118.83  4964.5 2116.01  4972.2 2116.25  4974.9 2115.63
  4975.3 2115.13  4979.5 2115.13  4979.9 2115.63  4985.1 2116.95  4992.9 2117.11
  5005.4 2117.25  5025.4 2115.67  5035.4 2116.47  5045.4 2118.51  5065.4 2126.38
  5071.5 2127.21  5135.4 2137.92  5155.4 2143.30  5175.4 2146.91  5195.4 2148.61
#Mann=4,-1,0
  4583.1    0.07       0  4974.9    0.05       0  4979.9    0.07       0
  5071.5     0.1       0
Bank Sta=4974.9,4979.9
Exp/Cntr=0.3,0.1

Type RM Length L Ch R = 1,33100,272,272,272
BEGIN DESCRIPTION:
Flat Rock Creek 64.1
END DESCRIPTION:
XS GIS Cut Line= 4
      1799142.47     13913494.39      1799581.36     13913605.92
      1799818.12     13913588.97      1800104.82     13913473.44
#Sta/Elev= 30
  4403.2 2141.45  4498.7 2137.79  4546.4 2134.36  4592.5 2133.12  4628.3 2131.00
  4777.2 2125.23  4839.2 2120.67  4909.8 2119.33  4959.9 2119.36  4970.0 2117.86
  4977.5 2113.58  4977.9 2113.08  4982.5 2113.58  5010.1 2113.95  5040.1 2117.02
  5060.2 2115.67  5070.2 2116.55  5077.1 2120.11  5082.1 2121.19  5089.3 2124.92
  5093.4 2124.92  5100.8 2127.01  5133.2 2130.13  5176.3 2138.14  5195.1 2140.80
  5206.5 2143.68  5230.2 2148.01  5294.9 2149.35  5330.5 2151.01  5402.5 2154.75
#Mann=5,-1,0
  4403.2    0.07       0  4977.5    0.05       0  4982.5    0.07       0
  5206.5     0.1       0  5330.5    0.07       0
Bank Sta=4977.5,4982.5
Exp/Cntr=0.3,0.1

Type RM Length L Ch R = 1,32828,473,473,473
BEGIN DESCRIPTION:
Flat Rock Creek 64.0
END DESCRIPTION:
XS GIS Cut Line= 4
      1799080.85     13913583.11      1799443.62     13913782.60
      1799825.00     13913825.00      1800124.96     13913675.02
#Sta/Elev= 30
  4196.2 2141.24  4317.5 2136.55  4326.5 2136.93  4361.1 2134.29  4599.7 2126.43
  4661.9 2125.58  4893.3 2112.14  4903.4 2112.06  4923.5 2114.17  4933.6 2113.93
  4948.7 2110.82  4953.7 2114.67  4963.7 2110.58  4988.9 2108.01  4989.3 2107.51
  4993.9 2108.01  5007.9 2109.38  5047.0 2109.56  5052.6 2111.31  5069.4 2111.72
  5083.4 2114.05  5119.7 2116.30  5142.1 2120.71  5158.8 2122.23  5189.6 2127.64
  5217.5 2130.01  5239.9 2133.55  5273.7 2141.81  5298.6 2148.44  5329.3 2151.07
#Mann=4,-1,0
  4196.2    0.07       0  4988.9    0.05       0  4993.9    0.07       0
  5273.7     0.1       0
Bank Sta=4988.9,4993.9
Exp/Cntr=0.3,0.1

Type RM Length L Ch R = 1,32355,451,451,451
BEGIN DESCRIPTION:
Flat Rock Creek 63.0
END DESCRIPTION:
XS GIS Cut Line= 3
      1799446.80     13914552.49      1800225.00     13914025.00
      1800324.97     13914025.00
#Sta/Elev= 30
  4059.5 2132.48  4063.7 2131.27  4114.5 2129.94  4222.4 2128.37  4243.4 2128.95
  4359.3 2125.73  4581.8 2123.63  4697.6 2119.55  4733.9 2121.29  4740.5 2119.85
  4755.5 2119.35  4776.5 2118.84  4782.5 2119.82  4848.4 2118.09  4920.3 2112.44
  4927.1 2110.00  4935.2 2108.72  4963.4 2107.11  4977.2 2104.11  4979.9 2102.01
  4980.4 2101.51  4992.3 2102.01  4996.6 2109.16  5002.1 2109.16  5014.2 2120.74
  5029.6 2133.64  5049.6 2144.98  5059.6 2149.39  5069.6 2150.70  5099.6 2151.75
#Mann=4,-1,0
  4059.5    0.07       0  4979.9    0.05       0  4992.3    0.07       0
  5014.2     0.1       0
Bank Sta=4979.9,4992.3
Exp/Cntr=0.3,0.1