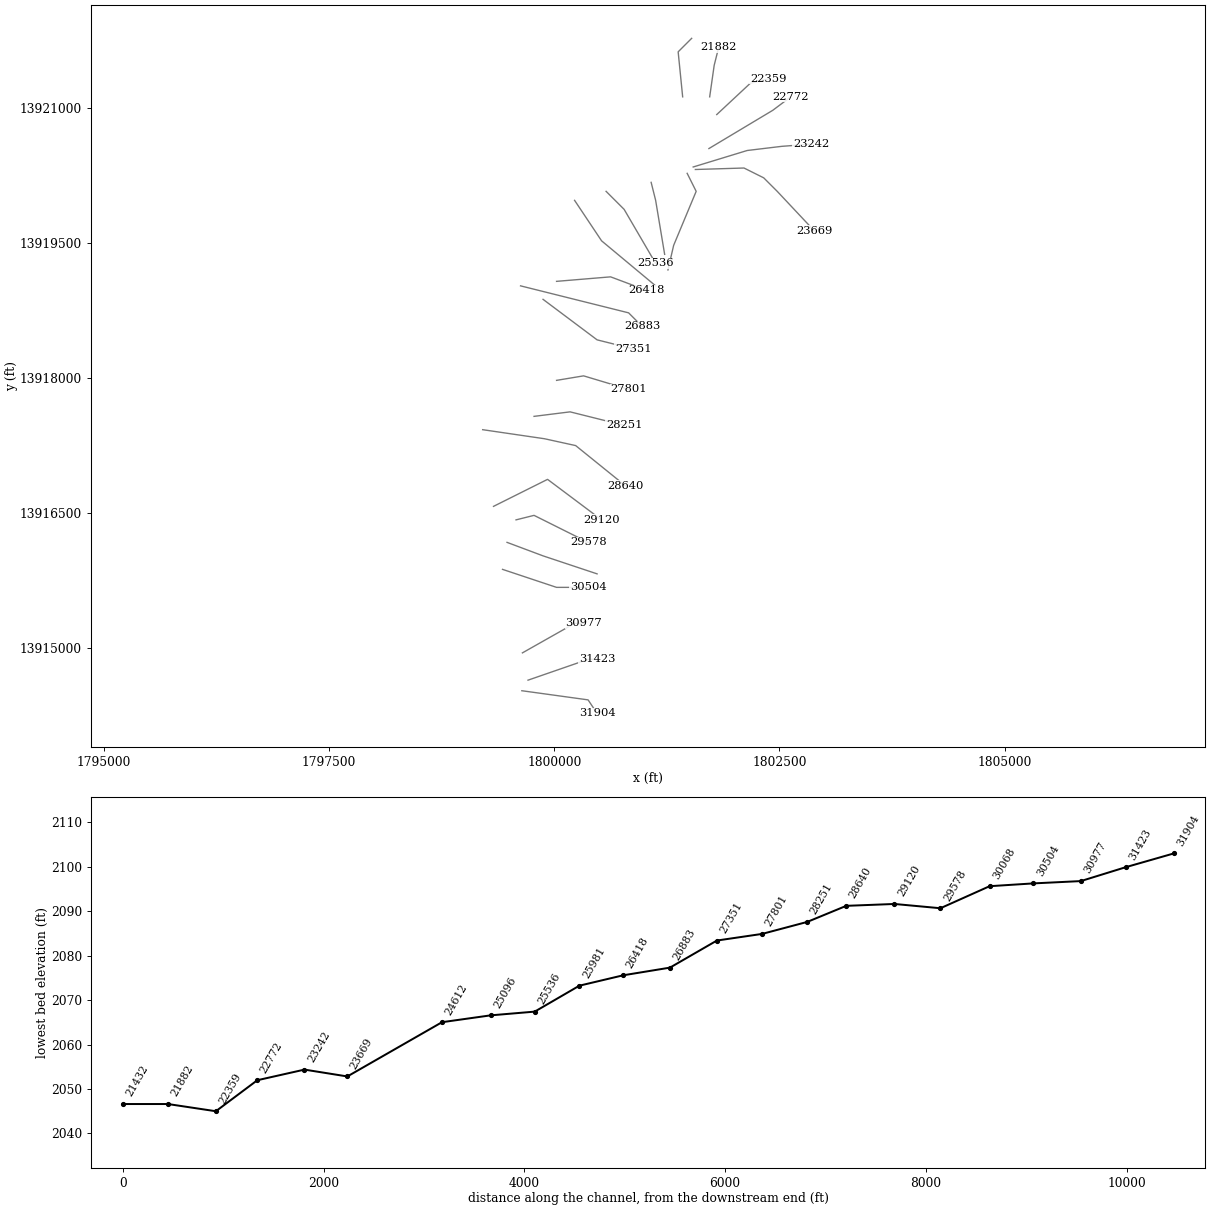
HEC-RAS study Flat Rock Creek.prj: Flat Rock Creek Base Level Engineering

--- Flat Rock Creek.g01 (geometry) --- (continued)

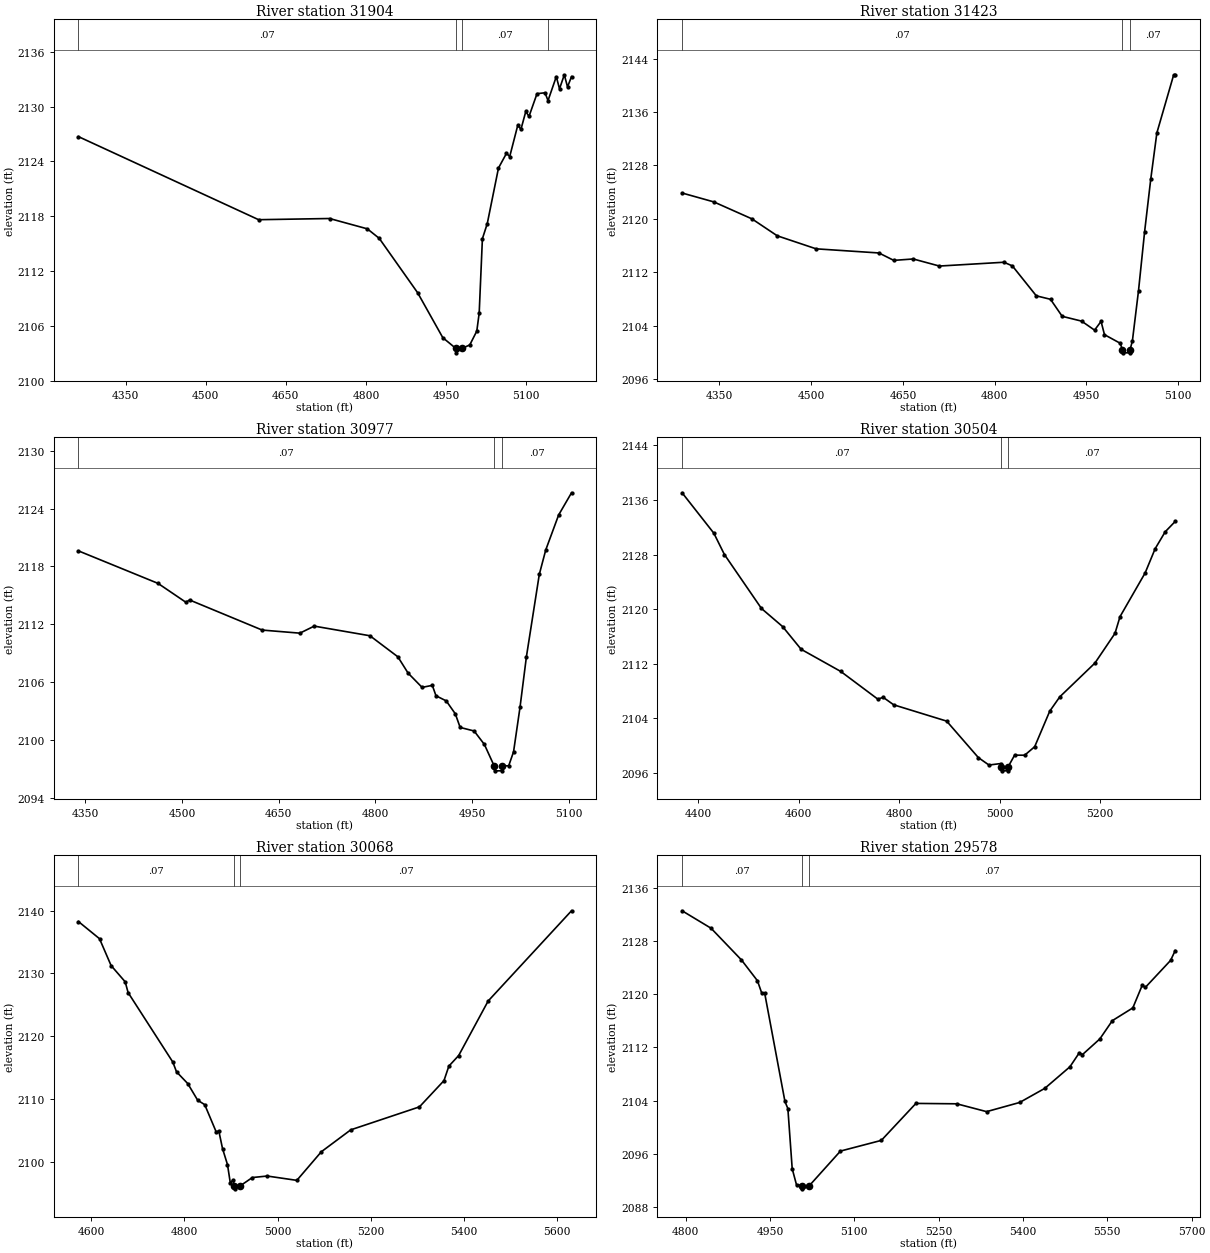
Type RM Length L Ch R = 1,31904,481,481,481
BEGIN DESCRIPTION:
Flat Rock Creek 62.0
END DESCRIPTION:
XS GIS Cut Line= 3
      1799639.37     13914526.65      1800375.00     13914425.00
      1800475.00     13914275.00
#Sta/Elev= 30
  4261.7 2126.72  4599.0 2117.62  4731.8 2117.75  4802.4 2116.62  4824.7 2115.58
  4896.5 2109.63  4943.7 2104.70  4967.8 2103.54  4968.3 2103.04  4980.3 2103.54
  4994.2 2103.91  5007.3 2105.42  5011.8 2107.40  5017.8 2115.54  5026.9 2117.19
  5047.9 2123.28  5062.9 2124.89  5068.9 2124.53  5083.9 2127.94  5090.0 2127.53
  5099.0 2129.47  5105.0 2128.93  5120.0 2131.42  5135.0 2131.52  5140.6 2130.66
  5156.1 2133.29  5162.1 2131.95  5171.1 2133.49  5177.1 2132.16  5184.6 2133.29
#Mann=4,-1,0
  4261.7    0.07       0  4967.8    0.05       0  4980.3    0.07       0
  5140.6     0.1       0
Bank Sta=4967.8,4980.3
Exp/Cntr=0.3,0.1

Type RM Length L Ch R = 1,31423,446,446,446
BEGIN DESCRIPTION:
Flat Rock Creek 61.0
END DESCRIPTION:
XS GIS Cut Line= 3
      1799708.10     13914644.06      1800375.00     13914875.00
      1800475.04     13914875.00
#Sta/Elev= 30
  4289.2 2123.87  4341.0 2122.54  4403.3 2120.00  4444.7 2117.46  4508.2 2115.51
  4610.8 2114.89  4635.1 2113.78  4666.9 2113.99  4709.6 2112.93  4815.1 2113.50
  4828.9 2112.95  4868.0 2108.47  4891.2 2107.95  4910.3 2105.40  4942.0 2104.68
  4963.2 2103.33  4973.8 2104.64  4979.4 2102.65  5005.0 2101.37  5008.7 2100.43
  5009.2 2099.93  5020.8 2099.93  5021.3 2100.43  5025.0 2101.72  5035.0 2109.24
  5045.0 2118.10  5055.0 2125.95  5065.0 2132.88  5092.5 2141.58  5095.0 2141.58
#Mann=3,-1,0
  4289.2    0.07       0  5008.7    0.05       0  5021.3    0.07       0
Bank Sta=5008.7,5021.3
Exp/Cntr=0.3,0.1

Type RM Length L Ch R = 1,30977,473,473,473
BEGIN DESCRIPTION:
Flat Rock Creek 60.0
END DESCRIPTION:
XS GIS Cut Line= 3
      1799645.84     13914947.17      1800225.00     13915275.00
      1800324.99     13915275.00
#Sta/Elev= 30
  4339.1 2119.61  4462.7 2116.24  4506.0 2114.28  4511.7 2114.52  4624.4 2111.40
  4682.9 2111.08  4705.2 2111.81  4791.7 2110.81  4835.0 2108.63  4850.9 2106.94
  4872.6 2105.46  4888.5 2105.67  4894.2 2104.59  4910.1 2104.06  4924.2 2102.72
  4931.7 2101.31  4953.4 2100.94  4969.3 2099.55  4984.6 2097.31  4985.1 2096.81
  4996.7 2096.81  4997.2 2097.31  5007.1 2097.34  5014.6 2098.78  5024.6 2103.38
  5034.6 2108.65  5054.6 2117.18  5064.6 2119.71  5084.6 2123.33  5104.6 2125.63
#Mann=3,-1,0
  4339.1    0.07       0  4984.6    0.05       0  4997.2    0.07       0
Bank Sta=4984.6,4997.2
Exp/Cntr=0.3,0.1

Type RM Length L Ch R = 1,30504,436,436,436
BEGIN DESCRIPTION:
Flat Rock Creek 59.0
END DESCRIPTION:
XS GIS Cut Line= 3
      1799424.99     13915875.00      1800025.00     13915675.00
      1800375.04     13915675.00
#Sta/Elev= 30
  4367.5 2137.06  4430.8 2131.13  4451.8 2128.01  4525.6 2120.10  4567.8 2117.44
  4604.7 2114.11  4683.7 2110.86  4757.5 2106.80  4768.1 2107.07  4789.1 2105.97
  4894.6 2103.58  4957.8 2098.23  4978.9 2097.14  5002.5 2097.36  5003.6 2096.79
  5004.1 2096.29  5015.9 2096.29  5016.4 2096.79  5030.0 2098.59  5050.0 2098.58
  5070.0 2099.83  5100.0 2105.04  5120.0 2107.14  5190.0 2112.09  5230.0 2116.45
  5240.0 2118.90  5290.0 2125.30  5310.0 2128.86  5330.0 2131.34  5350.0 2132.86
#Mann=3,-1,0
  4367.5    0.07       0  5003.6    0.05       0  5016.4    0.07       0
Bank Sta=5003.6,5016.4
Exp/Cntr=0.3,0.1

Type RM Length L Ch R = 1,30068,490,490,490
BEGIN DESCRIPTION:
Flat Rock Creek 58.0
END DESCRIPTION:
XS GIS Cut Line= 3
      1799474.99     13916175.00      1799875.00     13916025.00
      1800475.03     13915824.99
#Sta/Elev= 30
  4572.0 2138.25  4617.4 2135.51  4642.3 2131.23  4672.6 2128.64  4678.8 2126.93
  4774.9 2115.86  4782.9 2114.30  4807.0 2112.43  4828.3 2109.78  4843.5 2109.07
  4868.4 2104.68  4873.7 2104.91  4881.7 2102.08  4892.4 2099.52  4898.6 2096.53
  4904.0 2097.09  4907.3 2096.16  4907.8 2095.66  4920.2 2096.16  4945.8 2097.46
  4977.8 2097.70  5041.4 2097.01  5094.1 2101.57  5157.3 2105.06  5304.9 2108.72
  5357.6 2112.90  5368.1 2115.21  5389.2 2116.90  5452.5 2125.58  5631.7 2139.96
#Mann=3,-1,0
  4572.0    0.07       0  4907.3    0.05       0  4920.2    0.07       0
Bank Sta=4907.3,4920.2
Exp/Cntr=0.3,0.1

Type RM Length L Ch R = 1,29578,458,458,458
BEGIN DESCRIPTION:
Flat Rock Creek 57.0
END DESCRIPTION:
XS GIS Cut Line= 3
      1799575.03     13916425.01      1799775.00     13916475.00
      1800374.96     13916175.02
#Sta/Elev= 30
  4793.9 2132.59  4845.4 2129.96  4899.5 2125.18  4927.9 2122.05  4935.6 2120.17
  4940.8 2120.16  4976.8 2103.86  4982.0 2102.79  4989.7 2093.73  4997.4 2091.29
  5007.5 2091.20  5008.0 2090.70  5020.4 2091.20  5075.5 2096.39  5148.2 2098.00
  5209.7 2103.57  5282.3 2103.51  5335.4 2102.33  5394.1 2103.71  5438.9 2105.84
  5483.6 2109.09  5500.3 2111.21  5505.9 2110.93  5536.7 2113.28  5559.0 2116.04
  5595.4 2117.96  5612.1 2121.37  5617.7 2121.05  5662.5 2125.11  5670.8 2126.60
#Mann=3,-1,0
  4793.9    0.07       0  5007.5    0.05       0  5020.4    0.07       0
Bank Sta=5007.5,5020.4
Exp/Cntr=0.3,0.1

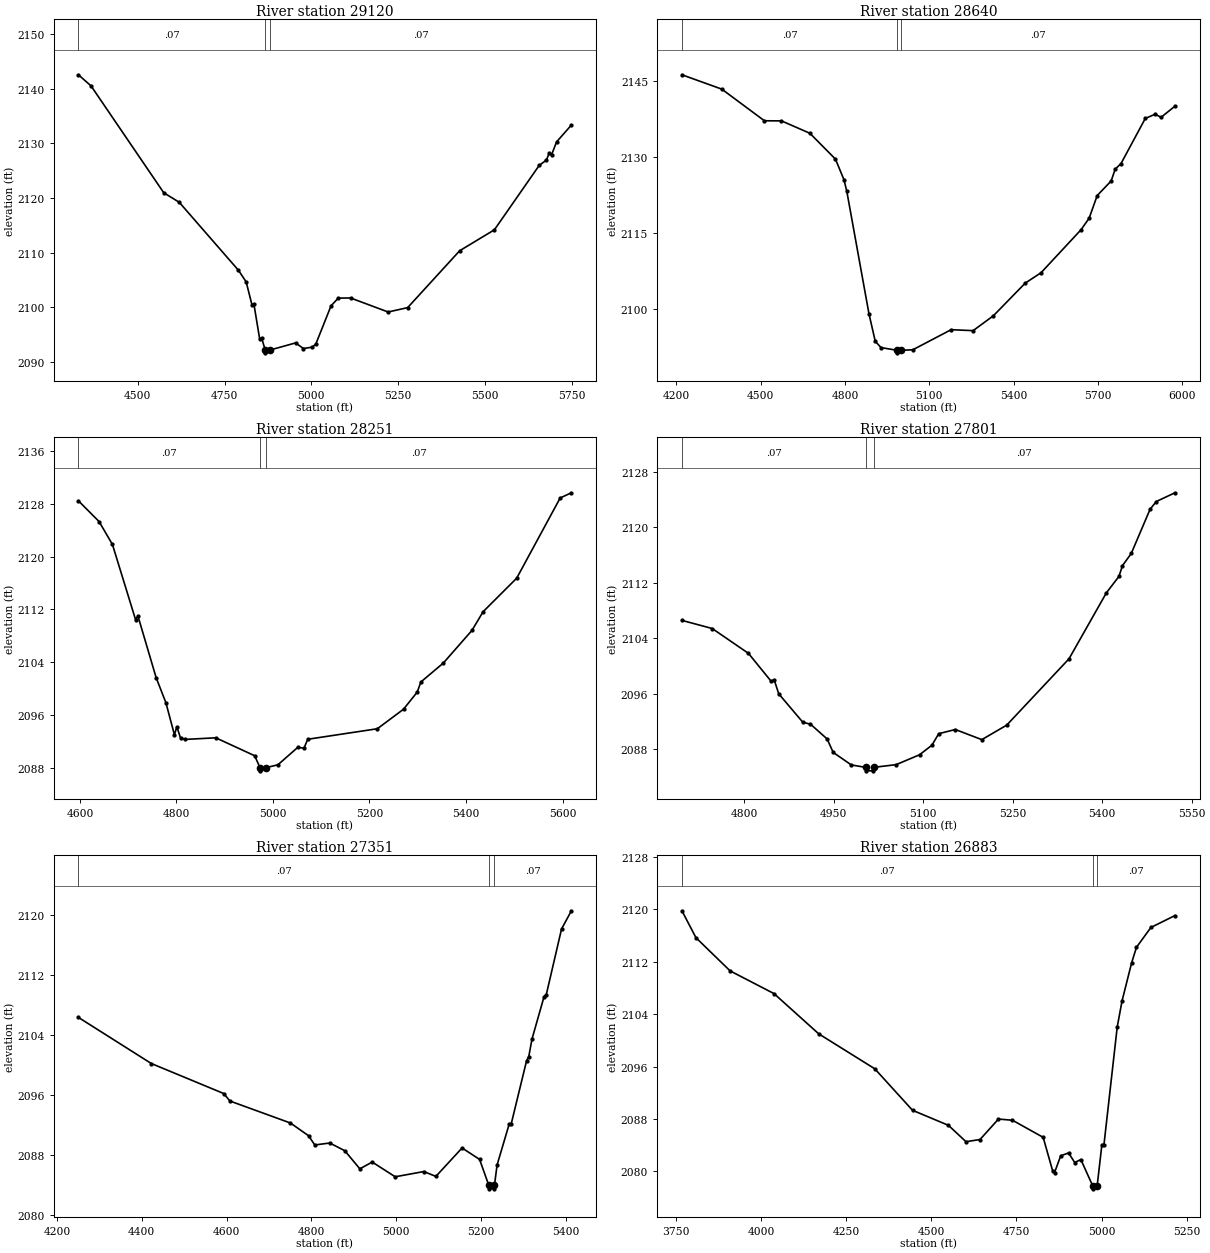
Type RM Length L Ch R = 1,29120,480,480,480
BEGIN DESCRIPTION:
Flat Rock Creek 56.0
END DESCRIPTION:
XS GIS Cut Line= 3
      1799324.97     13916574.98      1799925.00     13916875.00
      1800525.03     13916424.98
#Sta/Elev= 30
  4328.6 2142.58  4365.0 2140.55  4574.6 2120.98  4619.3 2119.23  4789.8 2106.79
  4812.2 2104.65  4829.0 2100.43  4834.5 2100.58  4851.3 2094.13  4856.9 2094.34
  4867.2 2092.16  4867.7 2091.66  4880.1 2092.16  4954.7 2093.48  4977.1 2092.45
  5002.6 2092.70  5013.0 2093.28  5056.8 2100.27  5077.6 2101.68  5113.0 2101.71
  5221.3 2099.14  5277.6 2099.94  5427.6 2110.36  5527.6 2114.19  5656.8 2125.99
  5677.6 2126.96  5685.9 2128.30  5692.2 2127.89  5706.8 2130.29  5749.5 2133.37
#Mann=3,-1,0
  4328.6    0.07       0  4867.2    0.05       0  4880.1    0.07       0
Bank Sta=4867.2,4880.1
Exp/Cntr=0.3,0.1

Type RM Length L Ch R = 1,28640,389,389,389
BEGIN DESCRIPTION:
Flat Rock Creek 55.1
END DESCRIPTION:
XS GIS Cut Line= 4
      1799204.67     13917426.89      1799890.04     13917326.48
      1800237.21     13917250.29      1800785.69     13916806.74
#Sta/Elev= 30
  4220.3 2146.24  4362.1 2143.40  4513.7 2137.14  4574.4 2137.12  4675.4 2134.67
  4766.4 2129.55  4796.7 2125.47  4806.8 2123.16  4885.7 2098.91  4907.9 2093.53
  4928.3 2092.28  4985.7 2091.74  4986.2 2091.24  4999.1 2091.74  5041.3 2091.84
  5177.8 2095.82  5255.9 2095.63  5328.0 2098.57  5441.5 2105.04  5497.5 2107.08
  5639.8 2115.59  5668.6 2117.87  5697.3 2122.35  5746.9 2125.24  5761.3 2127.57
  5782.1 2128.69  5868.4 2137.61  5903.6 2138.44  5924.4 2137.82  5973.8 2140.03
#Mann=3,-1,0
  4220.3    0.07       0  4985.7    0.05       0  4999.1    0.07       0
Bank Sta=4985.7,4999.1
Exp/Cntr=0.3,0.1

Type RM Length L Ch R = 1,28251,450,450,450
BEGIN DESCRIPTION:
Flat Rock Creek 55.0
END DESCRIPTION:
XS GIS Cut Line= 3
      1799775.04     13917575.00      1800175.00     13917625.00
      1800774.96     13917475.01
#Sta/Elev= 30
  4596.9 2128.42  4639.7 2125.29  4667.4 2121.83  4715.3 2110.48  4720.3 2111.01
  4758.1 2101.68  4778.3 2097.90  4795.9 2093.07  4800.9 2094.27  4808.5 2092.60
  4818.6 2092.37  4881.6 2092.61  4962.2 2089.90  4973.1 2088.12  4973.6 2087.62
  4986.5 2088.12  5010.3 2088.53  5051.5 2091.17  5064.4 2091.05  5072.1 2092.39
  5216.4 2093.98  5270.6 2096.93  5298.9 2099.51  5306.6 2101.05  5353.0 2103.90
  5412.3 2108.83  5435.5 2111.66  5505.1 2116.73  5595.2 2128.85  5618.4 2129.63
#Mann=3,-1,0
  4596.9    0.07       0  4973.1    0.05       0  4986.5    0.07       0
Bank Sta=4973.1,4986.5
Exp/Cntr=0.3,0.1

Type RM Length L Ch R = 1,27801,450,450,450
BEGIN DESCRIPTION:
Flat Rock Creek 54.0
END DESCRIPTION:
XS GIS Cut Line= 3
      1800025.03     13917975.01      1800325.00     13918025.00
      1800824.98     13917875.01
#Sta/Elev= 30
  4695.9 2106.58  4746.6 2105.41  4807.4 2101.83  4845.4 2097.81  4850.5 2098.02
  4858.1 2096.01  4898.6 2091.90  4911.3 2091.64  4939.2 2089.51  4949.3 2087.58
  4979.7 2085.77  5003.7 2085.42  5004.2 2084.92  5016.6 2084.92  5017.1 2085.42
  5054.8 2085.81  5094.0 2087.23  5114.8 2088.61  5126.2 2090.27  5154.0 2090.87
  5198.4 2089.41  5240.1 2091.50  5344.5 2101.05  5407.2 2110.56  5428.1 2112.90
  5434.1 2114.46  5448.9 2116.23  5480.3 2122.57  5490.7 2123.69  5522.0 2124.95
#Mann=3,-1,0
  4695.9    0.07       0  5003.7    0.05       0  5017.1    0.07       0
Bank Sta=5003.7,5017.1
Exp/Cntr=0.3,0.1

Type RM Length L Ch R = 1,27351,468,468,468
BEGIN DESCRIPTION:
Flat Rock Creek 53.0
END DESCRIPTION:
XS GIS Cut Line= 3
      1799874.99     13918875.01      1800475.00     13918425.00
      1800874.98     13918325.00
#Sta/Elev= 30
  4250.5 2106.33  4422.4 2100.17  4593.2 2096.16  4607.8 2095.16  4750.5 2092.22
  4793.2 2090.52  4807.8 2089.29  4843.2 2089.55  4878.6 2088.52  4914.1 2086.10
  4943.2 2087.01  4997.4 2085.04  5064.9 2085.74  5093.3 2085.09  5155.1 2088.89
  5196.4 2087.36  5217.9 2083.93  5218.4 2083.43  5231.0 2083.43  5231.5 2083.93
  5237.6 2086.61  5265.9 2092.03  5271.1 2092.14  5307.2 2100.55  5312.3 2101.09
  5320.0 2103.45  5348.4 2109.11  5353.5 2109.34  5389.6 2118.14  5412.8 2120.57
#Mann=3,-1,0
  4250.5    0.07       0  5217.9    0.05       0  5231.5    0.07       0
Bank Sta=5217.9,5231.5
Exp/Cntr=0.3,0.1

Type RM Length L Ch R = 1,26883,465,465,465
BEGIN DESCRIPTION:
Flat Rock Creek 52.0
END DESCRIPTION:
XS GIS Cut Line= 3
      1799625.02     13919024.99      1800825.00     13918725.00
      1800974.97     13918575.03
#Sta/Elev= 30
  3766.7 2119.77  3807.9 2115.66  3908.4 2110.59  4037.3 2107.13  4168.7 2100.99
  4333.6 2095.65  4444.4 2089.32  4550.1 2087.02  4601.6 2084.52  4642.8 2084.86
  4697.0 2087.98  4738.2 2087.80  4828.4 2085.19  4856.7 2079.99  4861.9 2079.82
  4879.9 2082.37  4903.1 2082.81  4921.1 2081.35  4939.2 2081.80  4973.6 2077.83
  4974.1 2077.33  4987.2 2077.83  5001.0 2084.08  5007.1 2084.08  5046.0 2102.01
  5060.2 2106.01  5088.5 2111.85  5102.6 2114.19  5145.0 2117.22  5215.7 2119.04
#Mann=3,-1,0
  3766.7    0.07       0  4973.6    0.05       0  4987.2    0.07       0
Bank Sta=4973.6,4987.2
Exp/Cntr=0.3,0.1

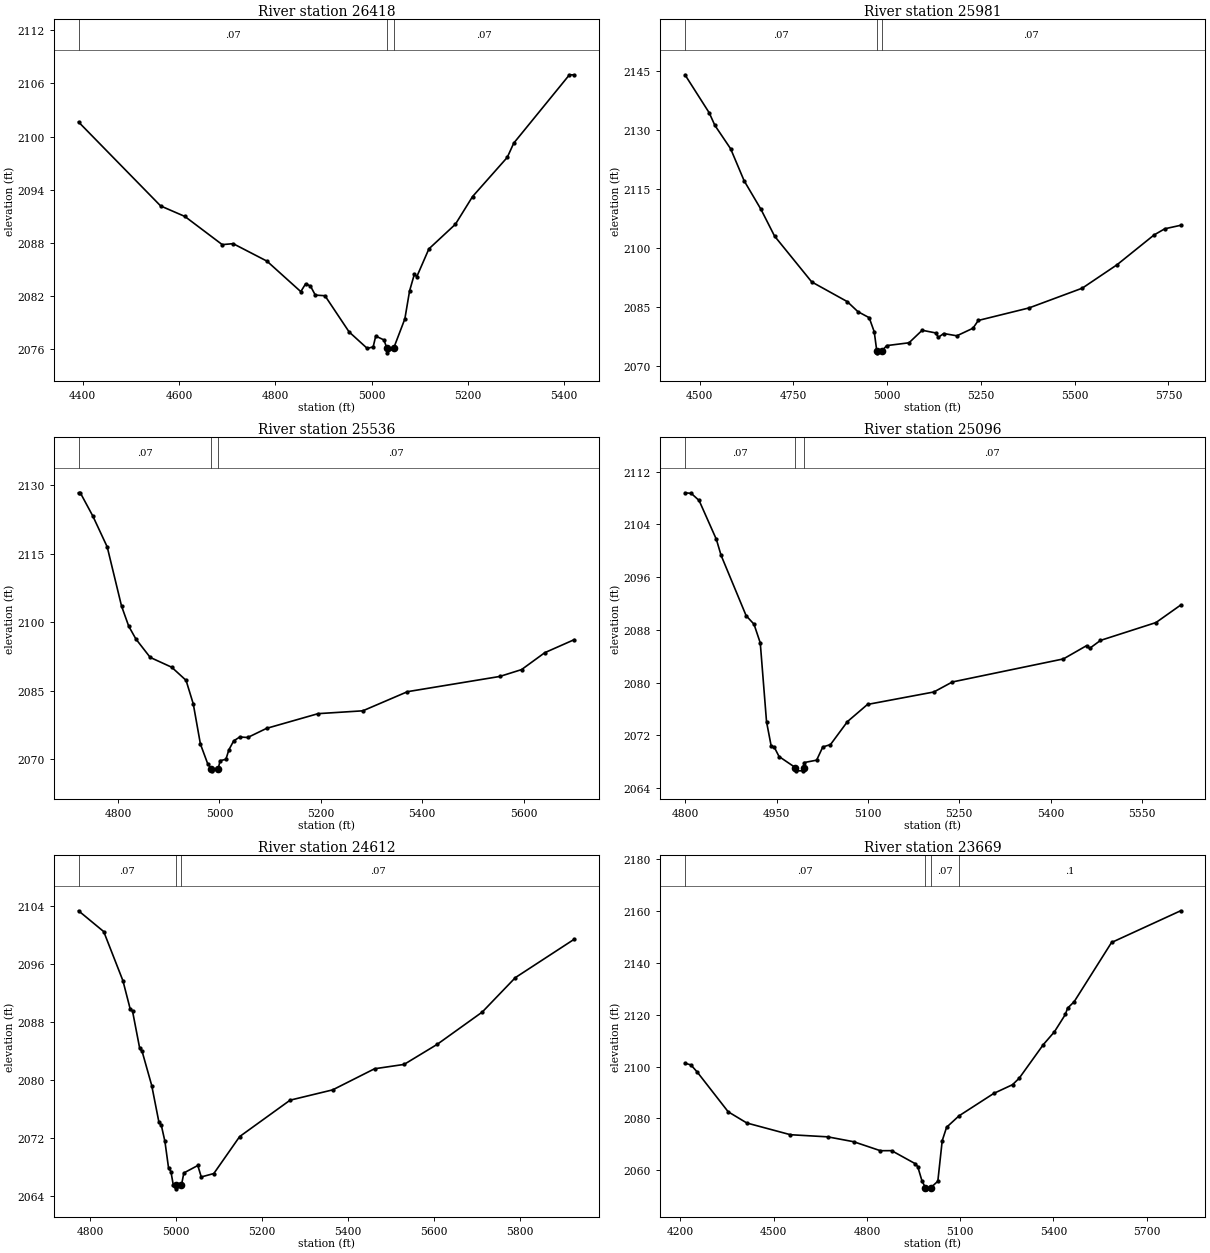
Type RM Length L Ch R = 1,26418,437,437,437
BEGIN DESCRIPTION:
Flat Rock Creek 51.0
END DESCRIPTION:
XS GIS Cut Line= 3
      1800025.01     13919075.00      1800625.00     13919125.00
      1801025.02     13918974.99
#Sta/Elev= 30
  4391.3 2101.64  4561.9 2092.17  4612.1 2090.99  4689.8 2087.81  4712.4 2087.92
  4782.6 2085.95  4852.9 2082.51  4862.9 2083.39  4873.0 2083.14  4883.0 2082.12
  4903.1 2082.05  4953.2 2077.97  4990.9 2076.11  5003.2 2076.28  5008.5 2077.50
  5025.4 2077.07  5032.0 2076.11  5032.5 2075.61  5045.6 2076.11  5069.0 2079.44
  5078.8 2082.59  5088.6 2084.45  5093.9 2084.21  5118.9 2087.33  5174.0 2090.11
  5209.6 2093.23  5281.7 2097.65  5295.1 2099.25  5410.8 2106.96  5420.6 2106.95
#Mann=3,-1,0
  4391.3    0.07       0  5032.0    0.05       0  5045.6    0.07       0
Bank Sta=5032,5045.6
Exp/Cntr=0.3,0.1

Type RM Length L Ch R = 1,25981,445,445,445
BEGIN DESCRIPTION:
Flat Rock Creek 50.0
END DESCRIPTION:
XS GIS Cut Line= 3
      1800224.98     13919975.02      1800525.00     13919525.00
      1801125.01     13919024.99
#Sta/Elev= 30
  4460.6 2144.08  4525.2 2134.40  4540.3 2131.20  4582.3 2125.25  4618.4 2117.08
  4663.4 2109.79  4699.5 2103.00  4798.6 2091.33  4893.3 2086.32  4921.8 2083.76
  4951.9 2082.22  4965.4 2078.61  4972.1 2073.77  4972.6 2073.27  4985.8 2073.77
  4998.5 2075.11  5058.1 2075.83  5093.2 2079.02  5129.7 2078.33  5136.2 2077.21
  5150.5 2078.19  5185.7 2077.61  5228.6 2079.53  5242.9 2081.52  5378.3 2084.71
  5520.2 2089.74  5612.6 2095.68  5711.5 2103.28  5740.2 2104.86  5782.5 2105.75
#Mann=3,-1,0
  4460.6    0.07       0  4972.1    0.05       0  4985.8    0.07       0
Bank Sta=4972.1,4985.8
Exp/Cntr=0.3,0.1

Type RM Length L Ch R = 1,25536,440,440,440
BEGIN DESCRIPTION:
Flat Rock Creek 49.0
END DESCRIPTION:
XS GIS Cut Line= 3
      1800575.00     13920075.00      1800775.00     13919875.00
      1801125.02     13919274.97
#Sta/Elev= 30
  4722.0 2128.30  4725.5 2128.30  4750.3 2123.19  4778.6 2116.45  4806.8 2103.52
  4821.0 2099.10  4835.1 2096.30  4863.4 2092.26  4905.8 2090.11  4934.1 2087.24
  4948.3 2082.09  4962.4 2073.30  4976.6 2069.03  4983.8 2067.93  4984.3 2067.43
  4997.5 2067.93  5001.3 2069.65  5012.7 2069.96  5018.5 2072.02  5028.0 2073.98
  5040.0 2074.84  5055.7 2074.73  5092.9 2076.73  5194.6 2079.95  5282.7 2080.57
  5370.8 2084.76  5552.7 2088.09  5595.7 2089.59  5641.6 2093.30  5699.5 2096.14
#Mann=3,-1,0
  4722.0    0.07       0  4983.8    0.05       0  4997.5    0.07       0
Bank Sta=4983.8,4997.5
Exp/Cntr=0.3,0.1

Type RM Length L Ch R = 1,25096,484,484,484
BEGIN DESCRIPTION:
Flat Rock Creek 48.0
END DESCRIPTION:
XS GIS Cut Line= 3
      1801075.00     13920175.02      1801125.00     13919975.00
      1801224.99     13919375.05
#Sta/Elev= 30
  4799.4 2108.80  4809.7 2108.71  4822.6 2107.63  4851.0 2101.72  4858.7 2099.31
  4899.9 2090.14  4912.8 2088.85  4923.1 2086.01  4933.4 2074.04  4941.1 2070.33
  4946.3 2070.14  4954.0 2068.76  4980.7 2067.09  4981.2 2066.59  4993.9 2066.59
  4994.4 2067.09  4995.3 2067.85  5015.7 2068.21  5025.8 2070.21  5038.5 2070.58
  5066.4 2074.07  5099.3 2076.67  5208.3 2078.56  5238.7 2080.08  5421.2 2083.58
  5459.2 2085.59  5464.3 2085.18  5482.1 2086.39  5573.3 2089.10  5613.8 2091.75
#Mann=3,-1,0
  4799.4    0.07       0  4980.7    0.05       0  4994.4    0.07       0
Bank Sta=4980.7,4994.4
Exp/Cntr=0.3,0.1

Type RM Length L Ch R = 1,24612,943,943,943
BEGIN DESCRIPTION:
Flat Rock Creek 47.0
END DESCRIPTION:
XS GIS Cut Line= 4
      1801475.00     13920274.99      1801575.00     13920075.00
      1801325.00     13919475.00      1801261.59     13919201.55
#Sta/Elev= 30
  4772.6 2103.40  4831.3 2100.53  4876.0 2093.76  4892.8 2089.89  4898.4 2089.56
  4915.1 2084.43  4920.7 2084.01  4943.1 2079.30  4959.9 2074.23  4965.4 2073.83
  4973.8 2071.60  4982.2 2067.97  4987.8 2067.43  4993.4 2065.55  4998.5 2065.55
  4999.0 2065.05  5012.3 2065.55  5017.9 2067.24  5050.4 2068.27  5058.5 2066.69
  5087.7 2067.16  5147.9 2072.26  5265.4 2077.28  5364.5 2078.70  5462.0 2081.61
  5530.8 2082.21  5607.7 2084.97  5712.8 2089.43  5789.9 2094.18  5926.9 2099.47
#Mann=3,-1,0
  4772.6    0.07       0  4998.5    0.05       0  5012.3    0.07       0
Bank Sta=4998.5,5012.3
Exp/Cntr=0.3,0.1

Type RM Length L Ch R = 1,23669,427,427,427
BEGIN DESCRIPTION:
Flat Rock Creek 45.0
END DESCRIPTION:
XS GIS Cut Line= 5
      1801566.10     13920317.71      1802106.00     13920334.22
      1802325.00     13920225.00      1802475.00     13920075.00
      1802883.54     13919639.54
#Sta/Elev= 30
  4214.9 2101.30  4233.8 2100.69  4253.8 2098.00  4353.9 2082.58  4413.9 2078.25
  4554.0 2073.73  4674.0 2072.91  4757.3 2071.03  4843.3 2067.56  4879.5 2067.58
  4955.1 2062.57  4963.4 2061.44  4977.4 2055.81  4988.2 2053.34  4988.7 2052.84
  5005.8 2053.34  5028.1 2055.78  5042.2 2071.42  5056.3 2076.61  5096.1 2081.00
  5208.4 2089.70  5268.3 2093.04  5289.8 2095.54  5367.5 2108.53  5403.1 2113.46
  5438.3 2120.16  5445.2 2122.55  5466.6 2125.07  5586.8 2147.93  5809.0 2160.17
#Mann=4,-1,0
  4214.9    0.07       0  4988.2    0.05       0  5005.8    0.07       0
  5096.1     0.1       0
Bank Sta=4988.2,5005.8
Exp/Cntr=0.3,0.1

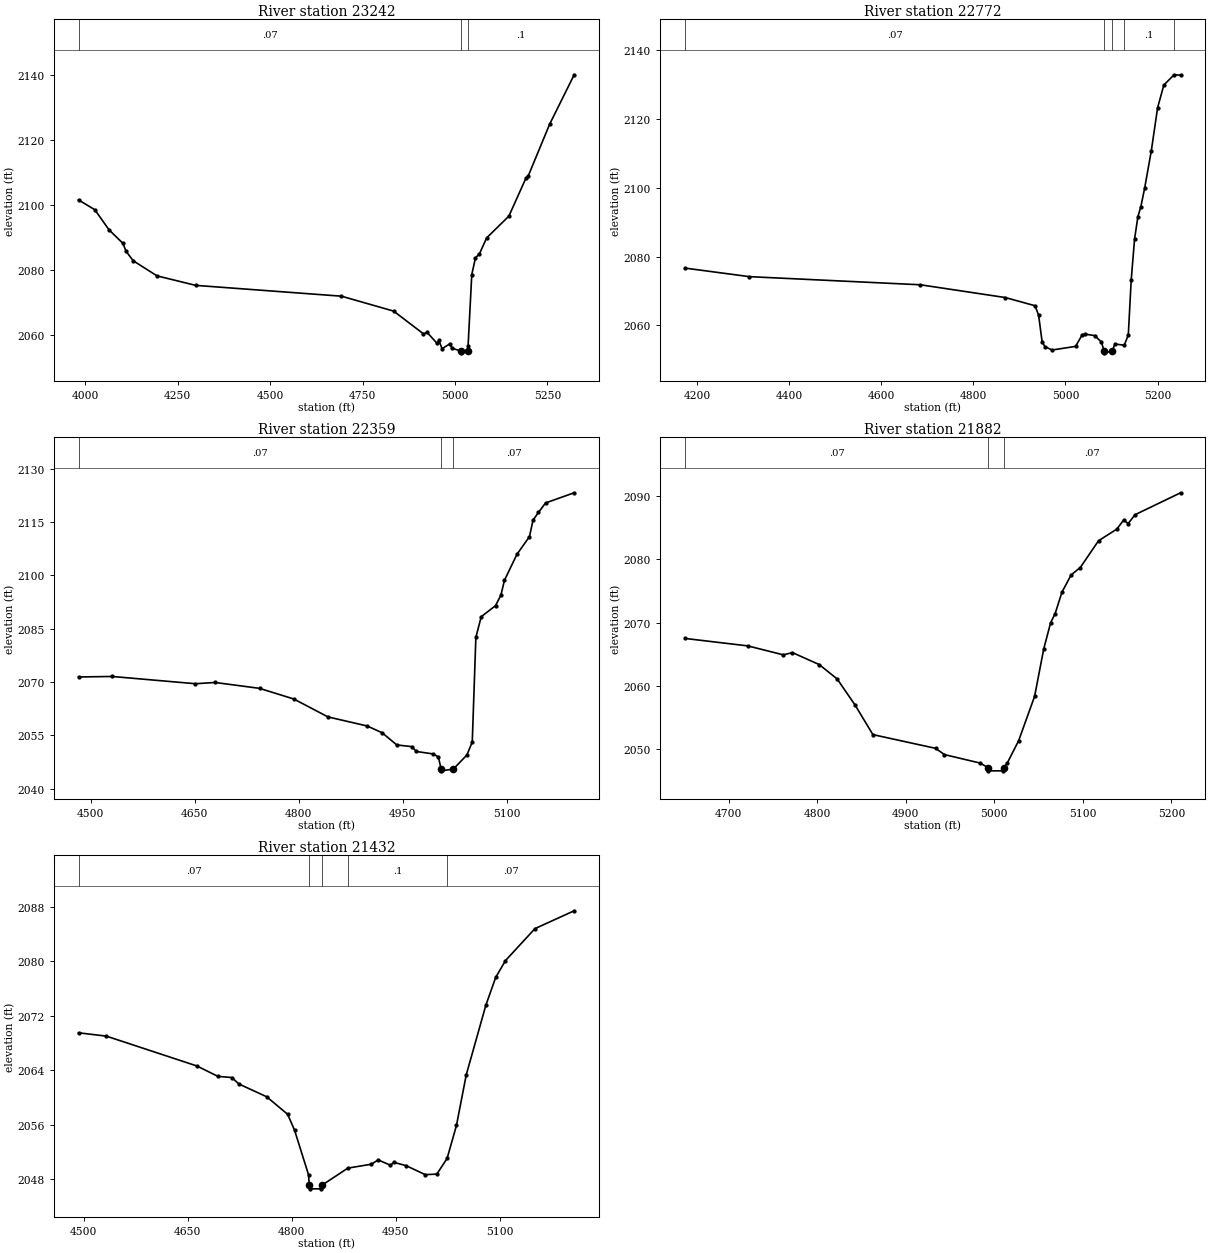
Type RM Length L Ch R = 1,23242,470,470,470
BEGIN DESCRIPTION:
Flat Rock Creek 44.0
END DESCRIPTION:
XS GIS Cut Line= 4
      1801542.06     13920345.75      1802141.49     13920528.81
      1802525.00     13920575.00      1802851.03     13920599.66
#Sta/Elev= 30
  3982.1 2101.57  4026.3 2098.53  4064.4 2092.36  4102.4 2088.13  4110.6 2085.72
  4130.0 2082.79  4194.3 2078.13  4298.9 2075.20  4693.0 2071.86  4834.0 2067.26
  4914.6 2060.25  4924.6 2060.67  4951.6 2057.29  4956.6 2058.20  4964.9 2055.66
  4985.1 2057.09  4992.6 2055.80  5016.4 2054.88  5016.9 2054.38  5034.0 2054.88
  5035.3 2056.44  5045.3 2078.55  5055.3 2083.70  5065.9 2084.90  5085.4 2089.83
  5145.6 2096.57  5192.3 2108.44  5197.4 2108.82  5255.9 2124.95  5322.1 2140.18
#Mann=3,-1,0
  3982.1    0.07       0  5016.4    0.05       0  5034.0     0.1       0
Bank Sta=5016.4,5034
Exp/Cntr=0.3,0.1

Type RM Length L Ch R = 1,22772,413,413,413
BEGIN DESCRIPTION:
Flat Rock Creek 43.0
END DESCRIPTION:
XS GIS Cut Line= 3
      1801716.61     13920550.43      1802425.00     13920975.00
      1802625.02     13921125.01
#Sta/Elev= 30
  4174.1 2076.66  4313.7 2074.17  4685.2 2071.80  4869.7 2068.08  4933.9 2065.70
  4941.7 2062.97  4949.4 2055.14  4955.3 2053.83  4970.8 2052.81  5021.9 2053.87
  5036.4 2057.25  5042.7 2057.43  5063.5 2057.01  5078.1 2055.12  5083.9 2052.49
  5084.4 2051.99  5101.5 2052.49  5107.3 2054.56  5127.6 2054.21  5136.4 2057.17
  5142.7 2073.15  5150.0 2085.12  5157.3 2091.67  5163.5 2094.44  5171.9 2099.92
  5186.4 2110.83  5200.0 2123.33  5213.5 2129.93  5235.7 2132.93  5250.0 2132.82
#Mann=5,-1,0
  4174.1    0.07       0  5083.9    0.05       0  5101.5    0.07       0
  5127.6     0.1       0  5235.7    0.07       0
Bank Sta=5083.9,5101.5
Exp/Cntr=0.3,0.1

Type RM Length L Ch R = 1,22359,477,477,477
BEGIN DESCRIPTION:
Flat Rock Creek 42.0
END DESCRIPTION:
XS GIS Cut Line= 3
      1801803.49     13920928.02      1802175.00     13921275.00
      1802375.00     13921325.00
#Sta/Elev= 30
  4482.7 2071.40  4531.1 2071.54  4651.3 2069.50  4679.6 2069.85  4743.6 2068.20
  4793.0 2065.21  4842.3 2060.17  4899.0 2057.61  4920.5 2055.70  4941.5 2052.29
  4963.0 2051.82  4969.8 2050.45  4993.6 2049.77  5001.4 2048.95  5005.4 2045.51
  5005.9 2045.01  5023.1 2045.51  5042.6 2049.48  5050.3 2053.12  5055.5 2082.53
  5063.2 2088.34  5083.8 2091.44  5091.6 2094.40  5096.7 2098.58  5114.7 2105.87
  5132.8 2110.87  5137.9 2115.49  5145.7 2117.65  5156.0 2120.32  5197.2 2123.18
#Mann=3,-1,0
  4482.7    0.07       0  5005.4    0.05       0  5023.1    0.07       0
Bank Sta=5005.4,5023.1
Exp/Cntr=0.3,0.1

Type RM Length L Ch R = 1,21882,450,450,450
BEGIN DESCRIPTION:
Flat Rock Creek 41.0
END DESCRIPTION:
XS GIS Cut Line= 3
      1801725.00     13921124.97      1801775.00     13921475.00
      1801824.99     13921674.96
#Sta/Elev= 30
  4650.8 2067.50  4721.5 2066.33  4762.0 2064.91  4772.1 2065.27  4802.4 2063.38
  4822.6 2061.12  4842.8 2057.02  4863.0 2052.34  4933.7 2050.18  4943.8 2049.19
  4984.2 2047.85  4993.0 2047.13  4993.5 2046.63  5010.2 2046.63  5010.7 2047.13
  5014.7 2047.85  5027.6 2051.39  5045.6 2058.37  5055.9 2065.84  5063.7 2069.98
  5068.8 2071.42  5076.5 2074.80  5086.9 2077.52  5097.2 2078.68  5117.8 2082.90
  5138.4 2084.73  5146.1 2086.15  5151.3 2085.61  5159.0 2087.00  5210.5 2090.46
#Mann=3,-1,0
  4650.8    0.07       0  4993.0    0.05       0  5010.7    0.07       0
Bank Sta=4993,5010.7
Exp/Cntr=0.3,0.1

Type RM Length L Ch R = 1,21432,450,450,450
BEGIN DESCRIPTION:
Flat Rock Creek 40.0
END DESCRIPTION:
XS GIS Cut Line= 3
      1801425.00     13921125.04      1801375.00     13921625.00
      1801525.01     13921775.01
#Sta/Elev= 30
  4492.5 2069.51  4532.7 2069.02  4663.3 2064.64  4693.5 2063.12  4713.6 2062.95
  4723.6 2062.01  4763.8 2060.13  4794.0 2057.56  4804.0 2055.22  4824.1 2048.70
  4825.3 2047.13  4825.8 2046.63  4842.5 2046.63  4843.0 2047.13  4880.9 2049.67
  4914.6 2050.24  4924.6 2050.87  4942.2 2050.09  4947.2 2050.51  4964.8 2050.03
  4992.4 2048.71  5009.1 2048.79  5023.9 2051.09  5037.4 2055.92  5051.5 2063.34
  5079.8 2073.56  5094.0 2077.64  5108.1 2080.10  5150.5 2084.78  5207.1 2087.40
#Mann=5,-1,0
  4492.5    0.07       0  4825.3    0.05       0  4843.0    0.07       0
  4880.9     0.1       0  5023.9    0.07       0
Bank Sta=4825.3,4843
Exp/Cntr=0.3,0.1