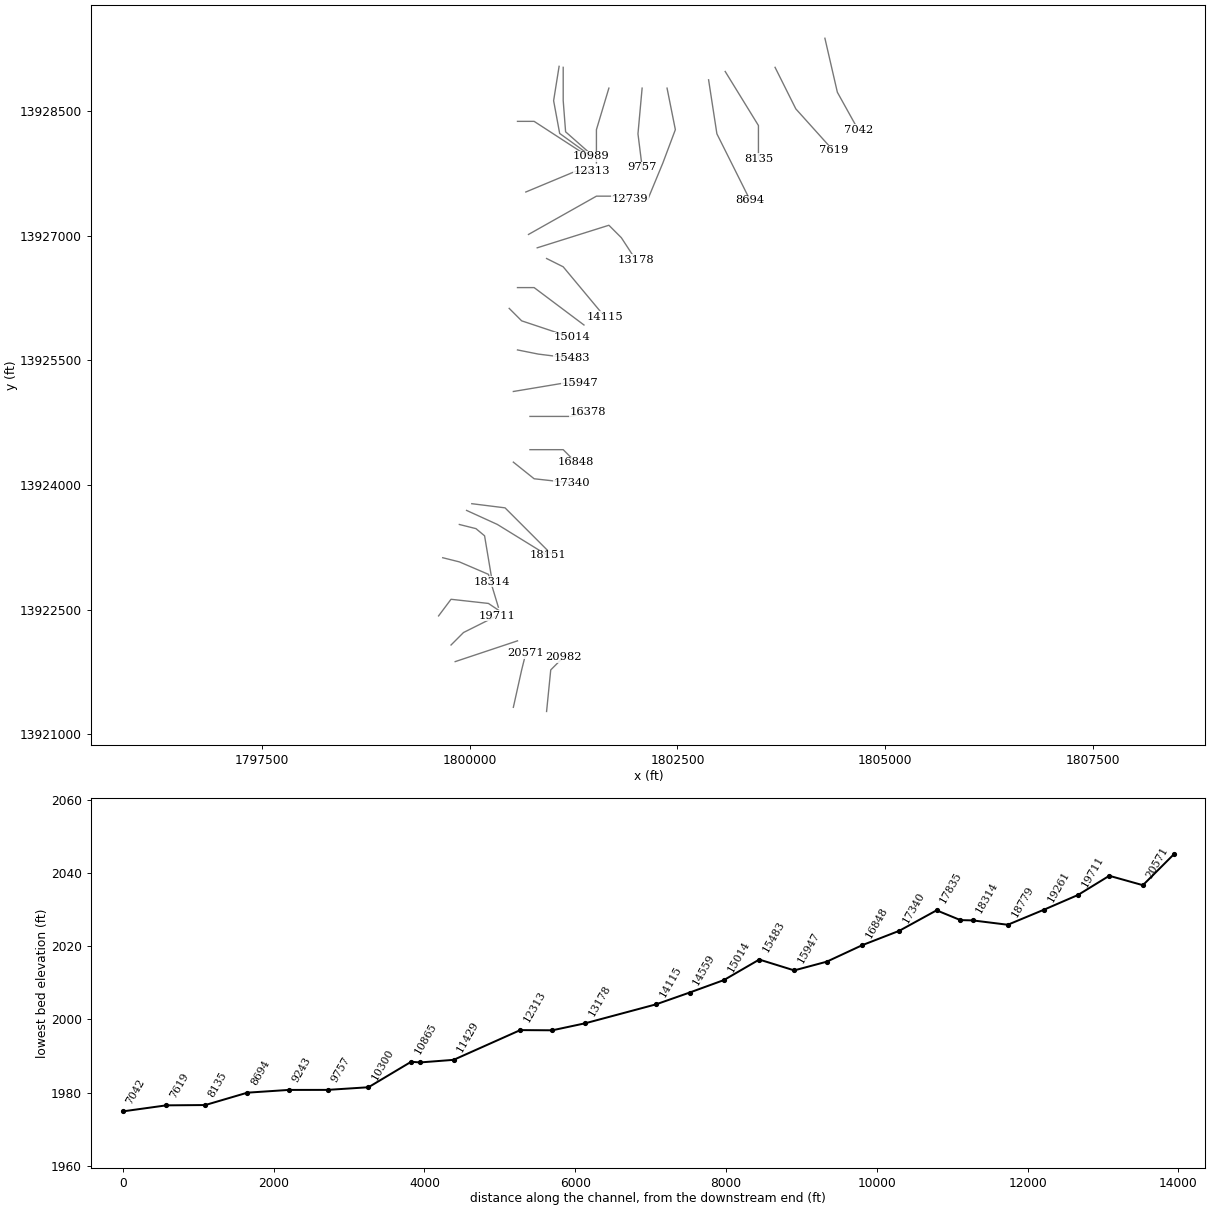
HEC-RAS study Flat Rock Creek.prj: Flat Rock Creek Base Level Engineering

--- Flat Rock Creek.g01 (geometry) --- (continued)

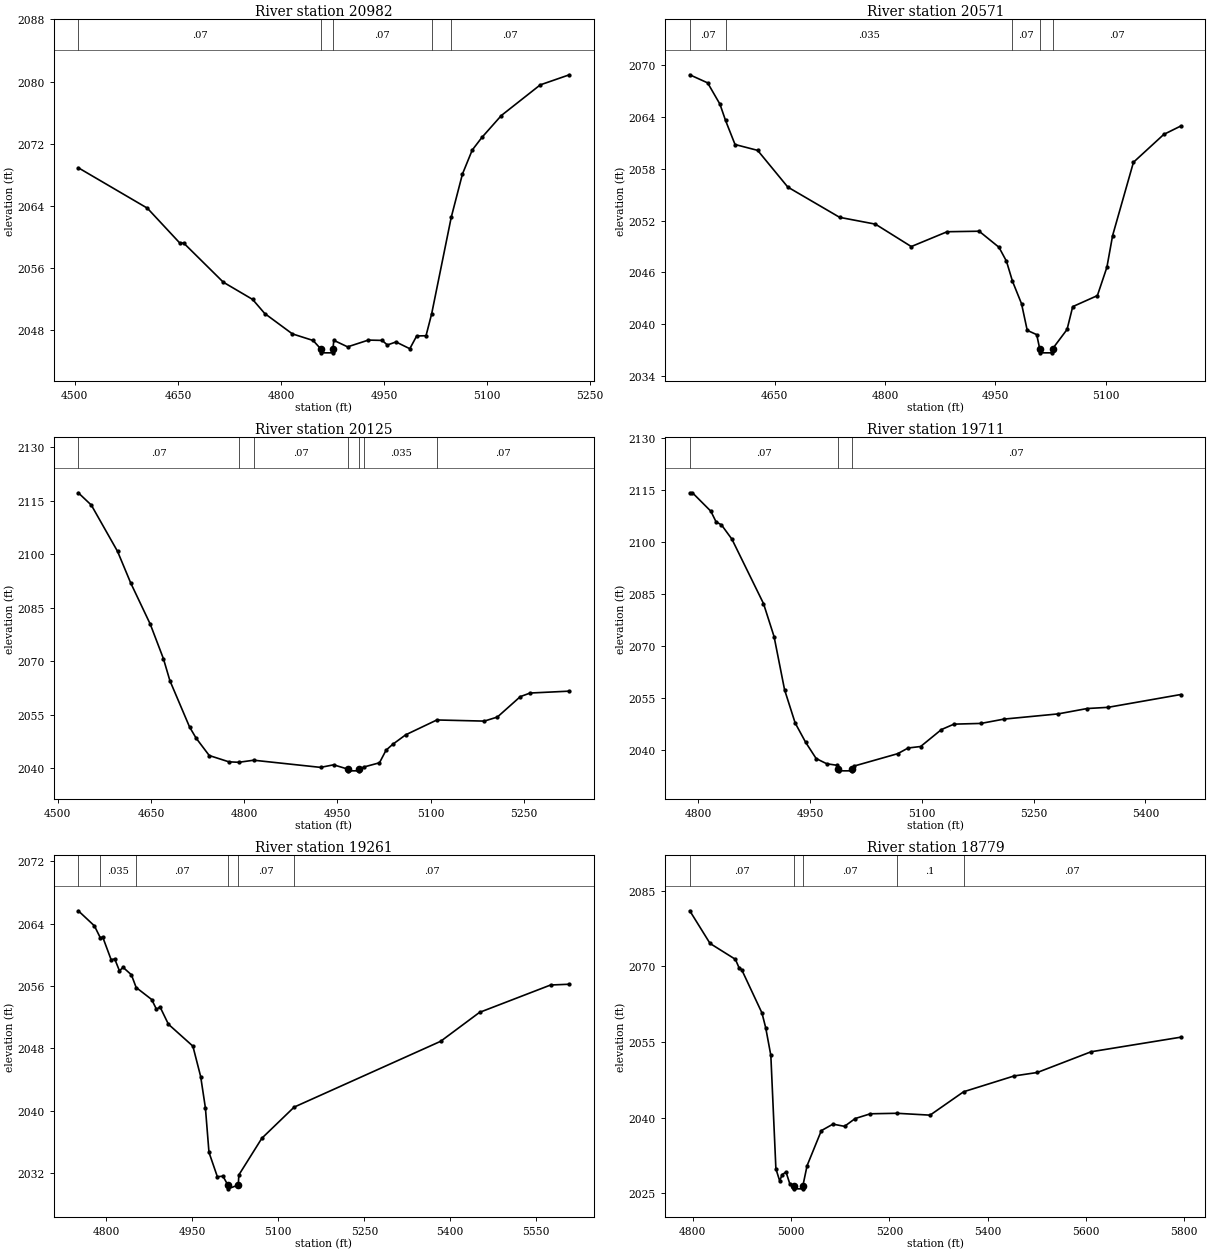
Type RM Length L Ch R = 1,20982,411,411,411
BEGIN DESCRIPTION:
Flat Rock Creek 39.0
END DESCRIPTION:
XS GIS Cut Line= 3
      1800925.00     13921275.03      1800975.00     13921775.00
      1801125.00     13921925.00
#Sta/Elev= 30
  4505.0 2068.92  4605.5 2063.72  4653.2 2059.19  4658.2 2059.25  4716.0 2054.20
  4758.7 2051.98  4776.3 2050.17  4816.5 2047.55  4846.7 2046.70  4857.9 2045.61
  4858.4 2045.11  4875.1 2045.11  4875.6 2045.61  4876.8 2046.72  4896.9 2045.88
  4927.1 2046.75  4947.2 2046.71  4954.7 2046.12  4967.3 2046.51  4987.4 2045.64
  4997.4 2047.28  5011.0 2047.31  5019.2 2050.13  5047.7 2062.55  5064.0 2068.11
  5078.2 2071.19  5092.3 2072.82  5120.6 2075.64  5177.2 2079.58  5219.6 2080.88
#Mann=5,-1,0
  4505.0    0.07       0  4857.9    0.05       0  4875.6    0.07       0
  5019.2     0.1       0  5047.7    0.07       0
Bank Sta=4857.9,4875.6
Exp/Cntr=0.3,0.1

Type RM Length L Ch R = 1,20571,446,446,446
BEGIN DESCRIPTION:
Flat Rock Creek 38.0
END DESCRIPTION:
XS GIS Cut Line= 3
      1800525.00     13921325.01      1800625.00     13921775.00
      1800674.99     13921974.98
#Sta/Elev= 30
  4534.8 2068.92  4559.1 2067.98  4575.8 2065.51  4583.4 2063.62  4596.3 2060.83
  4627.0 2060.15  4668.0 2055.89  4738.4 2052.38  4787.0 2051.59  4835.7 2048.99
  4884.4 2050.71  4927.9 2050.77  4954.8 2048.91  4965.0 2047.29  4973.2 2044.96
  4985.5 2042.35  4993.2 2039.27  5006.1 2038.77  5010.1 2037.16  5010.6 2036.66
  5027.4 2036.66  5027.9 2037.16  5047.3 2039.37  5055.0 2042.02  5088.5 2043.30
  5101.4 2046.58  5109.2 2050.27  5137.5 2058.77  5178.7 2062.00  5201.9 2062.98
#Mann=5,-1,0
  4534.8    0.07       0  4583.4   0.035       0  4973.2    0.07       0
  5010.1    0.05       0  5027.9    0.07       0
Bank Sta=5010.1,5027.9
Exp/Cntr=0.3,0.1

Type RM Length L Ch R = 1,20125,414,414,414
BEGIN DESCRIPTION:
Flat Rock Creek 37.0
END DESCRIPTION:
XS GIS Cut Line= 3
      1799825.04     13921875.01      1800275.00     13922025.00
      1800574.98     13922124.99
#Sta/Elev= 30
  4533.0 2117.28  4554.0 2113.82  4596.2 2100.83  4617.3 2092.00  4648.9 2080.38
  4670.0 2070.73  4680.5 2064.52  4712.1 2051.55  4722.7 2048.40  4743.8 2043.53
  4775.4 2041.76  4791.3 2041.63  4815.4 2042.21  4923.0 2040.20  4944.0 2040.92
  4966.5 2039.73  4967.0 2039.23  4984.3 2039.23  4984.8 2039.73  4993.6 2040.35
  5017.8 2041.49  5028.4 2045.02  5038.9 2046.64  5060.0 2049.34  5110.2 2053.51
  5186.5 2053.19  5207.6 2054.33  5244.5 2060.06  5260.3 2061.07  5323.5 2061.60
#Mann=7,-1,0
  4533.0    0.07       0  4791.3   0.035       0  4815.4    0.07       0
  4966.5   0.035       0  4984.8    0.07       0  4993.6   0.035       0
  5110.2    0.07       0
Bank Sta=4966.5,4984.8
Exp/Cntr=0.3,0.1

Type RM Length L Ch R = 1,19711,450,450,450
BEGIN DESCRIPTION:
Flat Rock Creek 36.0
END DESCRIPTION:
XS GIS Cut Line= 3
      1799774.98     13922074.98      1799925.00     13922225.00
      1800325.02     13922425.01
#Sta/Elev= 30
  4788.3 2114.10  4791.9 2114.10  4816.6 2108.79  4823.7 2105.69  4830.8 2104.87
  4844.9 2100.74  4887.3 2082.19  4901.5 2072.67  4915.6 2057.35  4929.8 2047.79
  4943.9 2042.22  4958.0 2037.54  4972.2 2036.04  4986.3 2035.59  4987.8 2034.50
  4988.3 2034.00  5005.6 2034.00  5006.1 2034.50  5008.8 2035.37  5067.5 2038.94
  5081.5 2040.58  5098.3 2041.01  5126.2 2045.89  5143.0 2047.45  5179.3 2047.66
  5210.1 2048.90  5282.8 2050.40  5321.9 2051.95  5349.8 2052.29  5447.7 2055.99
#Mann=3,-1,0
  4788.3    0.07       0  4987.8    0.05       0  5006.1    0.07       0
Bank Sta=4987.8,5006.1
Exp/Cntr=0.3,0.1

Type RM Length L Ch R = 1,19261,482,482,482
BEGIN DESCRIPTION:
Flat Rock Creek 35.0
END DESCRIPTION:
XS GIS Cut Line= 4
      1799624.99     13922424.99      1799775.00     13922625.00
      1800225.00     13922575.00      1800353.12     13922488.97
#Sta/Elev= 30
  4750.8 2065.65  4778.9 2063.72  4789.1 2062.21  4793.5 2062.27  4808.1 2059.38
  4814.4 2059.47  4822.7 2057.94  4828.9 2058.40  4843.5 2057.44  4851.8 2055.81
  4878.9 2054.27  4887.3 2053.01  4893.5 2053.32  4908.1 2051.10  4950.8 2048.29
  4964.4 2044.39  4972.7 2040.35  4978.9 2034.67  4993.5 2031.55  5003.3 2031.61
  5011.8 2030.49  5012.3 2029.99  5030.1 2030.49  5031.0 2031.77  5071.2 2036.48
  5127.5 2040.47  5383.2 2048.91  5451.1 2052.62  5575.1 2056.13  5607.9 2056.23
#Mann=6,-1,0
  4750.8    0.07       0  4789.1   0.035       0  4851.8    0.07       0
  5011.8    0.05       0  5030.1    0.07       0  5127.5    0.07       0
Bank Sta=5011.8,5030.1
Exp/Cntr=0.3,0.1

Type RM Length L Ch R = 1,18779,465,465,465
BEGIN DESCRIPTION:
Flat Rock Creek 34.0
END DESCRIPTION:
XS GIS Cut Line= 4
      1799674.97     13923125.01      1799875.00     13923075.00
      1800225.00     13922925.00      1800344.62     13922530.20
#Sta/Elev= 30
  4793.8 2080.99  4835.1 2074.51  4886.6 2071.37  4894.3 2069.66  4899.5 2069.31
  4940.7 2060.74  4948.4 2057.78  4958.8 2052.32  4969.1 2029.83  4976.8 2027.44
  4981.9 2028.68  4989.7 2029.20  4997.4 2026.86  5005.1 2026.36  5005.6 2025.86
  5023.3 2025.86  5023.8 2026.36  5032.6 2030.46  5061.6 2037.40  5085.2 2038.69
  5108.8 2038.25  5130.5 2039.80  5161.4 2040.74  5215.4 2040.84  5282.9 2040.47
  5351.2 2045.11  5453.9 2048.24  5501.2 2048.93  5610.7 2053.04  5793.3 2055.93
#Mann=5,-1,0
  4793.8    0.07       0  5005.1    0.05       0  5023.8    0.07       0
  5215.4     0.1       0  5351.2    0.07       0
Bank Sta=5005.1,5023.8
Exp/Cntr=0.3,0.1

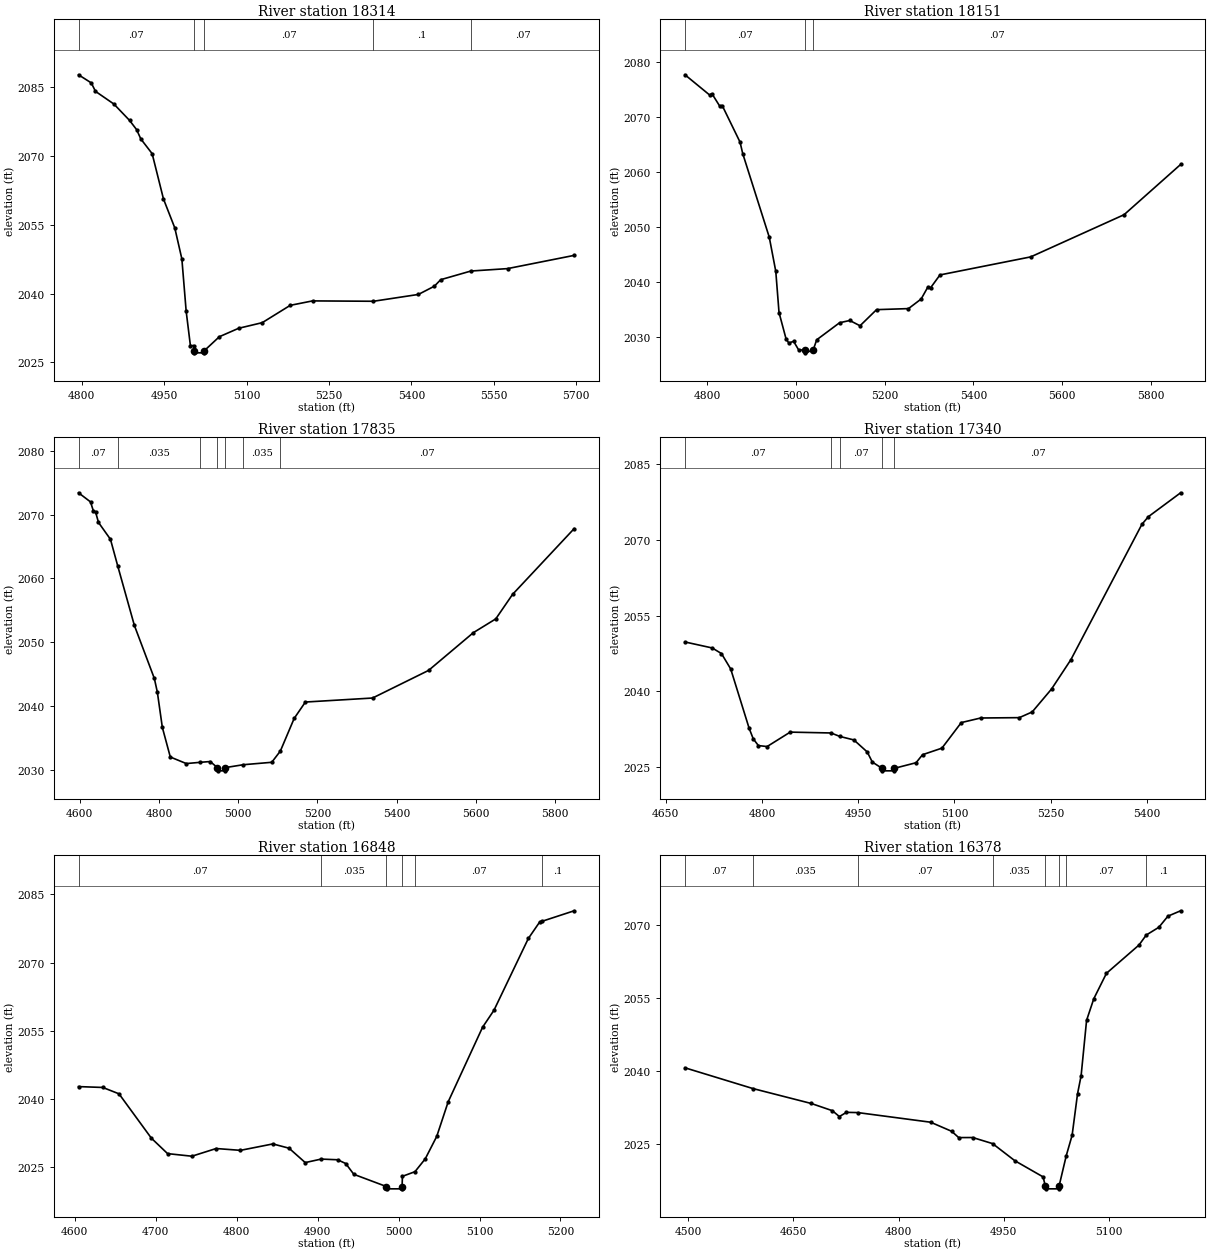
Type RM Length L Ch R = 1,18314,163,163,163
BEGIN DESCRIPTION:
Flat Rock Creek 33.0
END DESCRIPTION:
XS GIS Cut Line= 4
      1799874.99     13923525.00      1800075.00     13923475.00
      1800178.62     13923388.65      1800271.48     13922835.44
#Sta/Elev= 30
  4794.1 2087.76  4817.3 2085.99  4825.0 2084.14  4858.5 2081.37  4886.9 2077.81
  4899.8 2075.79  4907.5 2073.75  4928.1 2070.54  4948.7 2060.65  4969.3 2054.33
  4982.2 2047.54  4990.0 2036.15  4997.7 2028.64  5003.5 2028.64  5004.6 2027.55
  5005.1 2027.05  5022.8 2027.05  5023.3 2027.55  5050.4 2030.57  5085.5 2032.41
  5128.5 2033.64  5179.4 2037.42  5220.0 2038.39  5330.8 2038.31  5412.6 2039.80
  5441.7 2041.60  5453.2 2043.02  5508.1 2044.91  5574.9 2045.44  5696.1 2048.33
#Mann=5,-1,0
  4794.1    0.07       0  5004.6    0.05       0  5023.3    0.07       0
  5330.8     0.1       0  5508.1    0.07       0
Bank Sta=5004.6,5023.3
Exp/Cntr=0.3,0.1

Type RM Length L Ch R = 1,18151,316,316,316
BEGIN DESCRIPTION:
Mapping XS 661cd837
END DESCRIPTION:
XS GIS Cut Line= 3
      1799961.99     13923694.18      1800331.74     13923525.79
      1800937.61     13923152.55
#Sta/Elev= 30
  4749.3 2077.67  4804.8 2074.00  4810.3 2074.21  4827.9 2071.94  4833.4 2072.06
  4873.5 2065.43  4879.5 2063.36  4939.4 2048.15  4954.1 2041.94  4961.4 2034.46
  4977.2 2029.69  4983.4 2028.92  4994.3 2029.22  5005.7 2027.66  5019.3 2027.63
  5019.8 2027.13  5038.4 2027.63  5046.4 2029.50  5098.0 2032.60  5121.0 2033.01
  5144.1 2032.05  5181.4 2034.98  5253.4 2035.17  5281.9 2036.91  5297.3 2039.12
  5303.2 2038.95  5324.4 2041.29  5529.1 2044.57  5739.7 2052.24  5867.2 2061.37
#Mann=3,-1,0
  4749.3    0.07       0  5019.3    0.05       0  5038.4    0.07       0
Bank Sta=5019.3,5038.4
Exp/Cntr=0.3,0.1

Type RM Length L Ch R = 1,17835,495,495,495
BEGIN DESCRIPTION:
Flat Rock Creek 32.0
END DESCRIPTION:
XS GIS Cut Line= 3
      1800024.95     13923775.01      1800425.00     13923725.00
      1801025.01     13923124.99
#Sta/Elev= 30
  4596.8 2073.41  4627.1 2071.98  4634.6 2070.51  4639.7 2070.44  4647.2 2068.76
  4677.5 2066.11  4695.9 2061.92  4737.9 2052.60  4788.3 2044.29  4795.9 2042.14
  4808.5 2036.61  4828.6 2031.97  4869.0 2030.94  4904.8 2031.14  4929.4 2031.26
  4947.6 2030.30  4948.1 2029.80  4966.2 2029.80  4966.7 2030.30  5013.0 2030.76
  5084.8 2031.14  5106.5 2032.90  5141.4 2038.02  5169.7 2040.59  5339.4 2041.22
  5480.8 2045.55  5593.9 2051.47  5650.5 2053.63  5692.9 2057.47  5848.5 2067.79
#Mann=7,-1,0
  4596.8    0.07       0  4695.9   0.035       0  4904.8    0.07       0
  4947.6    0.05       0  4966.7    0.07       0  5013.0   0.035       0
  5106.5    0.07       0
Bank Sta=4947.6,4966.7
Exp/Cntr=0.3,0.1

Type RM Length L Ch R = 1,17340,492,492,492
BEGIN DESCRIPTION:
Flat Rock Creek 31.0
END DESCRIPTION:
XS GIS Cut Line= 3
      1800524.97     13924275.02      1800775.00     13924075.00
      1801225.04     13924025.00
#Sta/Elev= 30
  4679.8 2049.77  4722.3 2048.58  4736.7 2047.47  4751.1 2044.42  4779.9 2032.63
  4786.3 2030.55  4794.3 2029.22  4807.9 2029.03  4843.9 2031.89  4907.6 2031.72
  4921.4 2031.03  4943.2 2030.34  4964.0 2027.96  4972.0 2025.95  4987.1 2024.71
  4987.6 2024.21  5005.9 2024.21  5006.4 2024.71  5040.2 2025.82  5050.3 2027.41
  5080.5 2028.71  5110.7 2033.78  5140.9 2034.69  5201.2 2034.76  5221.3 2035.89
  5251.5 2040.44  5281.7 2046.27  5392.4 2073.10  5402.5 2074.62  5452.8 2079.36
#Mann=5,-1,0
  4679.8    0.07       0  4907.6   0.035       0  4921.4    0.07       0
  4987.1    0.05       0  5006.4    0.07       0
Bank Sta=4987.1,5006.4
Exp/Cntr=0.3,0.1

Type RM Length L Ch R = 1,16848,470,470,470
BEGIN DESCRIPTION:
Flat Rock Creek 30.0
END DESCRIPTION:
XS GIS Cut Line= 3
      1800725.04     13924425.00      1801125.00     13924425.00
      1801275.00     13924275.00
#Sta/Elev= 30
  4604.8 2042.75  4634.8 2042.56  4654.8 2041.16  4694.8 2031.41  4714.8 2028.02
  4744.8 2027.45  4774.8 2029.14  4804.8 2028.74  4844.8 2030.15  4864.8 2029.21
  4884.8 2026.05  4904.4 2026.82  4924.8 2026.67  4934.8 2025.84  4944.8 2023.47
  4985.1 2020.78  4985.6 2020.28  5003.9 2020.28  5004.4 2020.78  5004.8 2023.03
  5020.3 2024.05  5033.0 2026.87  5047.2 2031.81  5061.3 2039.40  5103.8 2055.80
  5117.9 2059.54  5160.3 2075.30  5174.5 2078.97  5177.6 2079.10  5216.9 2081.39
#Mann=6,-1,0
  4604.8    0.07       0  4904.4   0.035       0  4985.1   0.035       0
  5004.4   0.035       0  5020.3    0.07       0  5177.6     0.1       0
Bank Sta=4985.1,5004.4
Exp/Cntr=0.3,0.1

Type RM Length L Ch R = 1,16378,431,431,431
BEGIN DESCRIPTION:
Flat Rock Creek 29.0
END DESCRIPTION:
XS GIS Cut Line= 3
      1800724.99     13924825.00      1801225.00     13924825.00
      1801425.03     13924875.01
#Sta/Elev= 30
  4495.7 2040.67  4592.3 2036.41  4675.7 2033.33  4705.7 2031.85  4715.7 2030.64
  4725.7 2031.51  4742.0 2031.46  4845.7 2029.48  4875.7 2027.61  4885.7 2026.32
  4905.7 2026.33  4934.0 2025.08  4965.7 2021.56  5006.0 2018.23  5009.2 2016.28
  5009.7 2015.78  5028.1 2015.78  5028.6 2016.28  5039.0 2022.63  5047.3 2026.80
  5055.0 2035.31  5060.1 2039.04  5067.9 2050.43  5078.2 2054.88  5096.2 2060.10
  5142.6 2065.92  5152.9 2067.97  5170.9 2069.57  5183.8 2071.85  5201.9 2072.96
#Mann=8,-1,0
  4495.7    0.07       0  4592.3   0.035       0  4742.0    0.07       0
  4934.0   0.035       0  5009.2   0.035       0  5028.6   0.035       0
  5039.0    0.07       0  5152.9     0.1       0
Bank Sta=5009.2,5028.6
Exp/Cntr=0.3,0.1

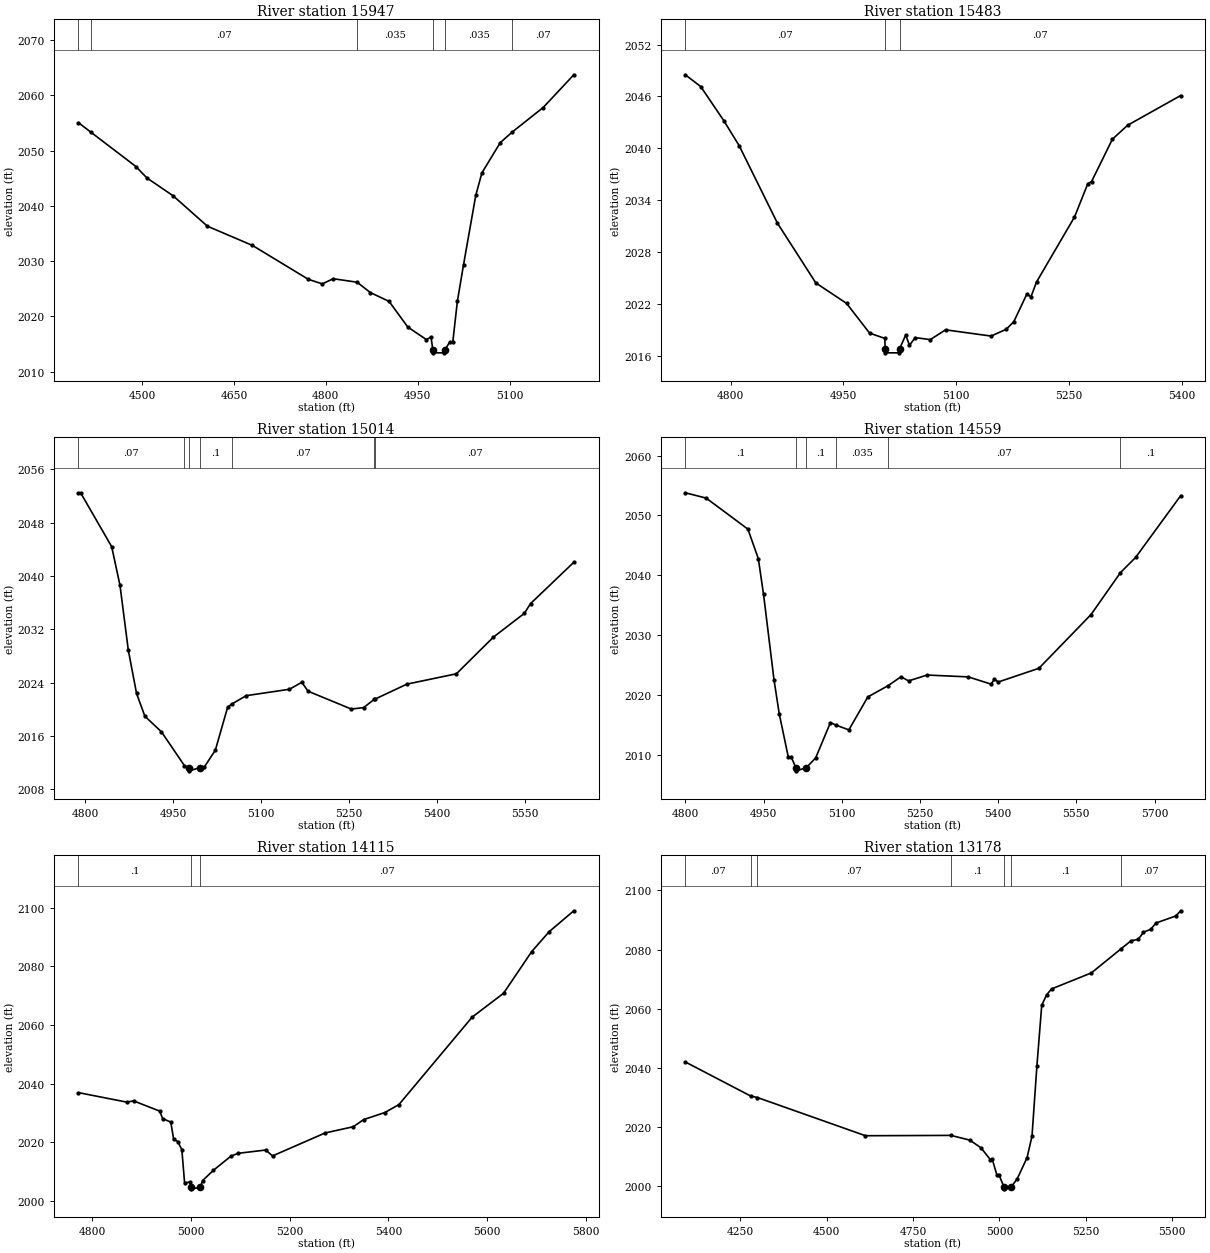
Type RM Length L Ch R = 1,15947,464,464,464
BEGIN DESCRIPTION:
Flat Rock Creek 28.0
END DESCRIPTION:
XS GIS Cut Line= 3
      1800524.99     13925125.00      1801125.00     13925225.00
      1801325.01     13925225.00
#Sta/Elev= 30
  4396.4 2055.07  4417.0 2053.32  4490.2 2047.13  4507.9 2045.08  4551.0 2041.82
  4606.8 2036.33  4680.3 2032.85  4771.5 2026.71  4794.3 2025.89  4812.1 2026.82
  4851.0 2026.19  4872.9 2024.30  4903.3 2022.71  4933.7 2018.08  4964.1 2015.80
  4971.7 2016.26  4974.7 2013.90  4975.2 2013.40  4993.6 2013.40  4994.1 2013.90
  5002.2 2015.35  5007.2 2015.35  5014.7 2022.74  5024.7 2029.33  5044.7 2041.90
  5054.7 2045.99  5084.7 2051.46  5104.5 2053.41  5154.7 2057.82  5204.7 2063.75
#Mann=6,-1,0
  4396.4     0.1       0  4417.0    0.07       0  4851.0   0.035       0
  4974.7   0.035       0  4994.1   0.035       0  5104.5    0.07       0
Bank Sta=4974.7,4994.1
Exp/Cntr=0.3,0.1

Type RM Length L Ch R = 1,15483,469,469,469
BEGIN DESCRIPTION:
Flat Rock Creek 27.0
END DESCRIPTION:
XS GIS Cut Line= 3
      1800574.96     13925625.01      1800825.00     13925575.00
      1801224.99     13925525.00
#Sta/Elev= 30
  4739.9 2048.51  4760.3 2047.15  4790.9 2043.22  4811.3 2040.33  4862.3 2031.35
  4913.3 2024.44  4954.1 2022.08  4984.7 2018.64  5005.0 2018.03  5005.3 2016.86
  5005.8 2016.36  5024.3 2016.36  5024.8 2016.86  5032.7 2018.43  5037.7 2017.23
  5045.3 2018.12  5065.4 2017.89  5085.6 2019.02  5146.1 2018.30  5166.2 2019.08
  5176.3 2019.96  5193.9 2023.20  5199.0 2022.81  5206.5 2024.55  5256.9 2032.05
  5274.6 2035.91  5279.6 2036.16  5307.3 2041.06  5327.5 2042.67  5398.0 2046.11
#Mann=3,-1,0
  4739.9    0.07       0  5005.3    0.05       0  5024.8    0.07       0
Bank Sta=5005.3,5024.8
Exp/Cntr=0.3,0.1

Type RM Length L Ch R = 1,15014,455,455,455
BEGIN DESCRIPTION:
Flat Rock Creek 26.0
END DESCRIPTION:
XS GIS Cut Line= 3
      1800474.97     13926125.03      1800625.00     13925975.00
      1801224.97     13925775.01
#Sta/Elev= 30
  4788.4 2052.48  4792.0 2052.48  4845.0 2044.39  4859.2 2038.57  4873.3 2028.89
  4887.4 2022.37  4901.6 2018.95  4929.9 2016.61  4968.9 2011.56  4976.7 2011.26
  4977.2 2010.76  4996.2 2011.26  5003.2 2011.37  5021.7 2013.85  5042.7 2020.30
  5049.4 2020.76  5074.4 2022.04  5148.2 2023.00  5169.2 2024.05  5179.8 2022.71
  5253.6 2020.03  5274.6 2020.25  5292.8 2021.49  5294.4 2021.54  5348.4 2023.77
  5432.8 2025.32  5496.0 2030.83  5548.7 2034.39  5559.2 2035.85  5633.0 2042.05
#Mann=7,-1,0
  4788.4    0.07       0  4968.9     0.1       0  4976.7    0.05       0
  4996.2     0.1       0  5049.4    0.07       0  5292.8   0.035       0
  5294.4    0.07       0
Bank Sta=4976.7,4996.2
Exp/Cntr=0.3,0.1

Type RM Length L Ch R = 1,14559,444,444,444
BEGIN DESCRIPTION:
Flat Rock Creek 25.0
END DESCRIPTION:
XS GIS Cut Line= 3
      1800574.97     13926375.00      1800775.00     13926375.00
      1801374.98     13925925.02
#Sta/Elev= 30
  4800.0 2053.79  4840.0 2052.90  4920.0 2047.72  4940.0 2042.78  4950.0 2036.82
  4970.0 2022.60  4980.0 2016.92  4997.5 2009.64  5003.2 2009.64  5012.1 2007.85
  5012.6 2007.35  5031.7 2007.85  5050.0 2009.51  5078.2 2015.40  5089.1 2014.98
  5113.6 2014.19  5150.0 2019.69  5189.3 2021.60  5213.6 2023.06  5228.2 2022.37
  5263.6 2023.35  5342.7 2023.04  5386.5 2021.83  5392.7 2022.65  5400.0 2022.18
  5478.2 2024.48  5578.2 2033.46  5634.6 2040.46  5663.6 2042.99  5750.0 2053.30
#Mann=6,-1,0
  4800.0     0.1       0  5012.1    0.05       0  5031.7     0.1       0
  5089.1   0.035       0  5189.3    0.07       0  5634.6     0.1       0
Bank Sta=5012.1,5031.7
Exp/Cntr=0.3,0.1

Type RM Length L Ch R = 1,14115,937,937,937
BEGIN DESCRIPTION:
Flat Rock Creek 24.0
END DESCRIPTION:
XS GIS Cut Line= 3
      1800925.02     13926724.99      1801125.00     13926625.00
      1801624.99     13926025.01
#Sta/Elev= 30
  4771.6 2036.94  4869.4 2033.71  4883.4 2034.12  4936.5 2030.63  4942.1 2028.11
  4958.8 2026.88  4964.4 2021.23  4972.8 2020.24  4981.2 2017.53  4986.8 2006.15
  4998.4 2006.51  4999.1 2004.64  4999.6 2004.14  5018.7 2004.64  5023.2 2006.95
  5045.3 2010.47  5080.4 2015.23  5094.8 2016.24  5151.4 2017.37  5165.1 2015.36
  5271.8 2023.19  5329.1 2025.32  5349.9 2027.75  5392.9 2030.15  5421.5 2032.87
  5569.9 2062.66  5633.7 2070.81  5690.9 2085.05  5726.1 2091.79  5776.2 2098.94
#Mann=3,-1,0
  4771.6     0.1       0  4999.1    0.05       0  5018.7    0.07       0
Bank Sta=4999.1,5018.7
Exp/Cntr=0.3,0.1

Type RM Length L Ch R = 1,13178,439,439,439
BEGIN DESCRIPTION:
Flat Rock Creek 23.0
END DESCRIPTION:
XS GIS Cut Line= 4
      1800812.22     13926853.61      1801675.00     13927125.00
      1801825.00     13926975.00      1801998.61     13926709.51
#Sta/Elev= 30
  4090.8 2041.93  4280.3 2030.38  4299.5 2029.89  4612.3 2016.96  4859.7 2017.07
  4914.3 2015.47  4946.7 2012.86  4973.8 2008.85  4979.1 2009.06  4992.6 2003.68
  4998.8 2003.68  5013.7 1999.48  5014.2 1998.98  5033.3 1999.48  5051.8 2002.44
  5080.1 2009.56  5094.3 2016.84  5108.4 2040.44  5122.5 2061.15  5136.7 2064.65
  5150.8 2066.65  5266.2 2072.08  5353.2 2080.34  5380.8 2082.94  5401.9 2083.44
  5417.0 2085.86  5438.1 2086.84  5453.2 2088.97  5510.5 2091.35  5524.6 2093.11
#Mann=7,-1,0
  4090.8    0.07       0  4280.3     0.1       0  4299.5    0.07       0
  4859.7     0.1       0  5013.7    0.05       0  5033.3     0.1       0
  5353.2    0.07       0
Bank Sta=5013.7,5033.3
Exp/Cntr=0.3,0.1

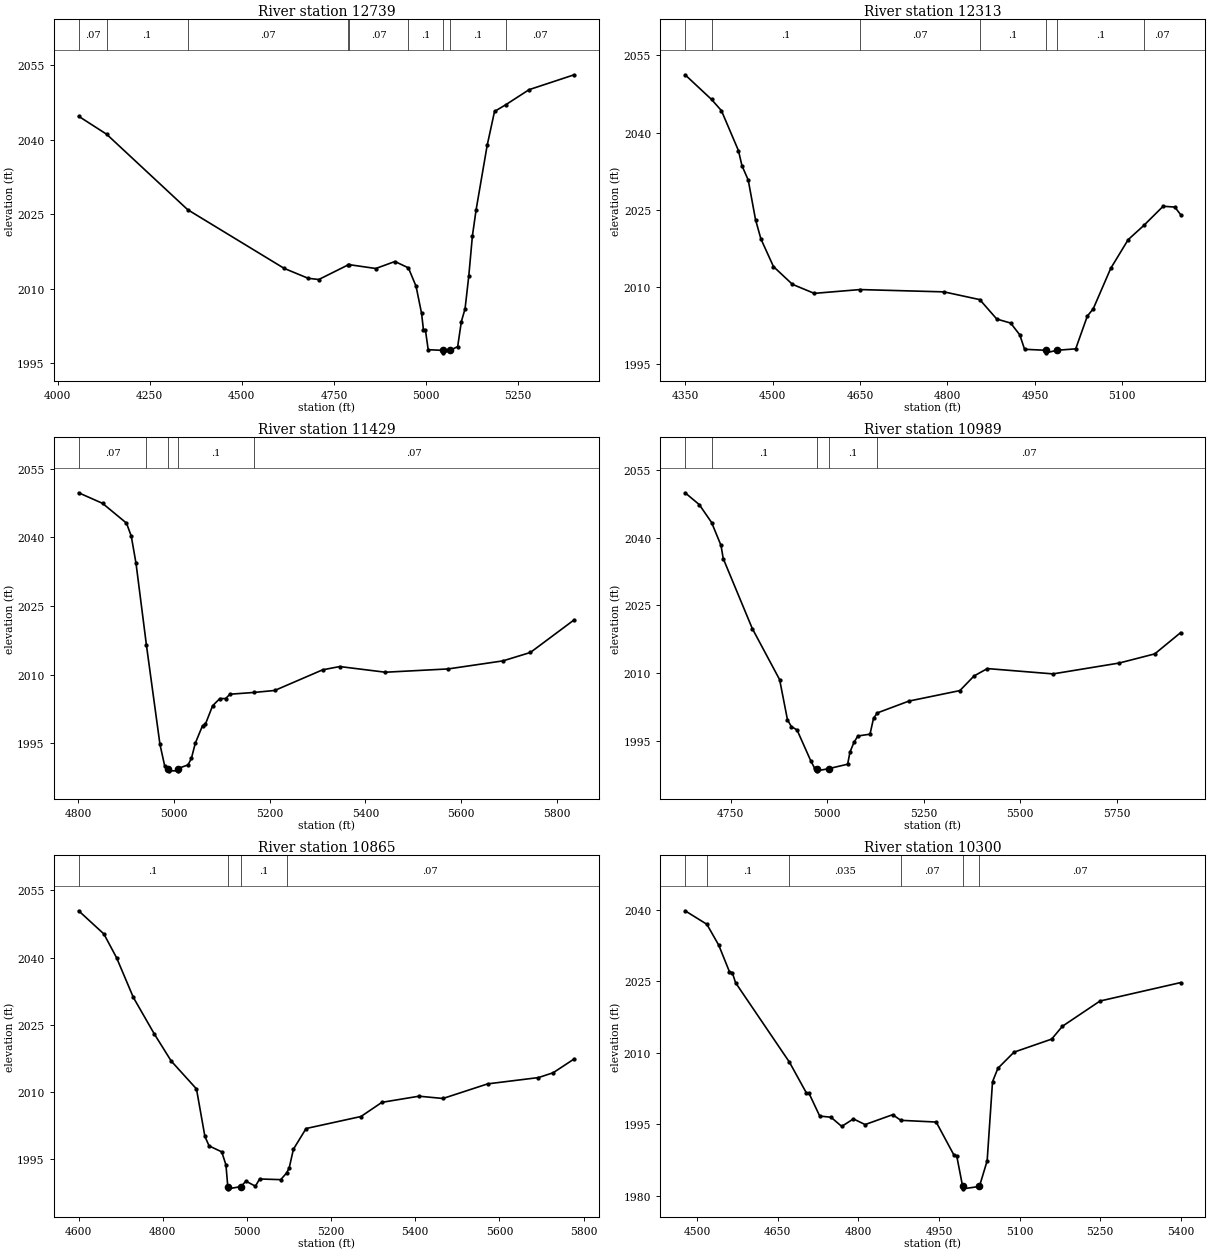
Type RM Length L Ch R = 1,12739,426,426,426
BEGIN DESCRIPTION:
Flat Rock Creek 22.0
END DESCRIPTION:
XS GIS Cut Line= 4
      1800707.31     13927014.30      1801525.00     13927475.00
      1801725.00     13927475.00      1801927.50     13927436.86
#Sta/Elev= 30
  4057.1 2044.74  4133.0 2041.12  4353.1 2025.90  4614.9 2014.07  4679.9 2012.08
  4708.7 2011.83  4788.2 2014.77  4790.7 2014.83  4863.4 2014.05  4915.3 2015.46
  4951.9 2014.18  4972.7 2010.46  4987.7 2004.98  4992.8 2001.63  4998.1 2001.63
  5005.6 1997.68  5045.8 1997.55  5046.3 1997.05  5065.4 1997.55  5085.6 1998.31
  5095.6 2003.36  5105.6 2005.92  5115.6 2012.44  5125.6 2020.64  5135.6 2025.88
  5165.6 2038.86  5185.6 2045.71  5216.1 2047.06  5279.4 2050.10  5401.7 2053.10
#Mann=9,-1,0
  4057.1    0.07       0  4133.0     0.1       0  4353.1    0.07       0
  4788.2     0.1       0  4790.7    0.07       0  4951.9     0.1       0
  5045.8    0.05       0  5065.4     0.1       0  5216.1    0.07       0
Bank Sta=5045.8,5065.4
Exp/Cntr=0.3,0.1

Type RM Length L Ch R = 1,12313,884,884,884
BEGIN DESCRIPTION:
Flat Rock Creek 21.0
END DESCRIPTION:
XS GIS Cut Line= 3
      1800675.03     13927525.01      1801275.00     13927775.00
      1801475.03     13927775.00
#Sta/Elev= 30
  4350.0 2051.24  4395.4 2046.43  4412.3 2044.26  4441.5 2036.48  4447.5 2033.55
  4458.3 2030.74  4470.8 2023.04  4480.0 2019.29  4501.6 2013.89  4534.1 2010.44
  4571.5 2008.68  4649.9 2009.42  4794.1 2008.97  4855.5 2007.46  4884.6 2003.68
  4908.4 2002.90  4924.1 2000.60  4932.3 1997.79  4968.5 1997.60  4969.0 1997.10
  4988.1 1997.60  5020.0 1997.88  5040.0 2004.27  5050.0 2005.65  5080.0 2013.53
  5110.0 2019.14  5136.9 2021.91  5170.0 2025.64  5190.0 2025.48  5200.0 2024.01
#Mann=7,-1,0
  4350.0   0.035       0  4395.4     0.1       0  4649.9    0.07       0
  4855.5     0.1       0  4968.5    0.05       0  4988.1     0.1       0
  5136.9    0.07       0
Bank Sta=4968.5,4988.1
Exp/Cntr=0.3,0.1

Type RM Length L Ch R = 1,11429,440,440,440
BEGIN DESCRIPTION:
Flat Rock Creek 20.0
END DESCRIPTION:
XS GIS Cut Line= 3
      1800574.99     13928375.00      1800775.00     13928375.00
      1801476.00     13927919.68
#Sta/Elev= 30
  4800.4 2049.77  4850.4 2047.46  4900.4 2043.14  4910.4 2040.31  4920.4 2034.32
  4942.1 2016.48  4970.4 1994.77  4980.4 1990.01  4988.1 1989.48  4988.6 1988.98
  5007.3 1988.98  5007.8 1989.48  5029.1 1990.28  5036.2 1991.72  5044.2 1995.00
  5059.4 1998.86  5065.3 1999.15  5080.5 2003.21  5095.6 2004.78  5107.7 2004.78
  5116.7 2005.73  5166.1 2006.11  5210.3 2006.55  5310.4 2011.06  5346.2 2011.78
  5441.6 2010.54  5572.8 2011.26  5687.4 2013.02  5744.8 2014.86  5836.3 2021.99
#Mann=5,-1,0
  4800.4    0.07       0  4942.1     0.1       0  4988.1    0.05       0
  5007.8     0.1       0  5166.1    0.07       0
Bank Sta=4988.1,5007.8
Exp/Cntr=0.3,0.1

Type RM Length L Ch R = 1,10989,124,124,124
BEGIN DESCRIPTION:
Mapping XS bef1034c
END DESCRIPTION:
XS GIS Cut Line= 4
      1801075.67     13929036.94      1801009.69     13928623.71
      1801082.61     13928229.61      1801459.31     13927957.07
#Sta/Elev= 30
  4631.7 2049.92  4668.4 2047.30  4700.4 2043.33  4724.8 2038.24  4730.5 2035.34
  4805.8 2019.83  4876.7 2008.49  4897.0 1999.60  4907.1 1998.09  4921.8 1997.35
  4957.7 1990.44  4967.8 1988.80  4973.4 1988.78  4973.9 1988.28  5004.6 1988.78
  5052.9 1989.75  5059.0 1992.44  5069.2 1994.57  5079.4 1996.00  5110.9 1996.41
  5120.0 1999.92  5129.8 2001.12  5211.6 2003.74  5343.8 2006.07  5380.5 2009.31
  5415.0 2010.95  5585.1 2009.77  5756.8 2012.18  5848.9 2014.21  5915.9 2018.92
#Mann=5,-1,0
  4631.7    0.07       0  4700.4     0.1       0  4973.4    0.05       0
  5004.6     0.1       0  5129.8    0.07       0
Bank Sta=4973.4,5004.6
Exp/Cntr=0.3,0.1

Type RM Length L Ch R = 1,10865,565,565,565
BEGIN DESCRIPTION:
Flat Rock Creek 19.0
END DESCRIPTION:
XS GIS Cut Line= 4
      1801125.00     13929024.96      1801125.00     13928625.00
      1801153.95     13928249.28      1801454.41     13927984.31
#Sta/Elev= 30
  4600.1 2050.45  4660.1 2045.28  4690.1 2040.01  4730.1 2031.13  4780.1 2022.95
  4820.1 2016.94  4880.1 2010.72  4900.1 2000.13  4910.1 1998.01  4940.1 1996.69
  4950.1 1993.78  4954.5 1988.94  4955.0 1988.44  4985.7 1988.94  4997.6 1990.16
  5020.1 1989.02  5030.1 1990.64  5080.3 1990.49  5094.2 1991.98  5100.4 1993.10
  5110.4 1997.27  5140.5 2001.89  5270.9 2004.57  5320.7 2007.73  5408.8 2009.10
  5465.7 2008.59  5572.0 2011.85  5692.5 2013.25  5727.6 2014.33  5777.5 2017.41
#Mann=4,-1,0
  4600.1     0.1       0  4954.5    0.05       0  4985.7     0.1       0
  5094.2    0.07       0
Bank Sta=4954.5,4985.7
Exp/Cntr=0.3,0.1

Type RM Length L Ch R = 1,10300,543,543,543
BEGIN DESCRIPTION:
Flat Rock Creek 18.0
END DESCRIPTION:
XS GIS Cut Line= 3
      1801674.99     13928774.96      1801525.00     13928275.00
      1801525.00     13927874.97
#Sta/Elev= 30
  4477.6 2039.74  4518.1 2036.91  4540.2 2032.54  4560.2 2026.95  4565.4 2026.80
  4571.5 2024.67  4671.8 2008.02  4702.9 2001.66  4708.1 2001.52  4728.1 1996.74
  4749.0 1996.50  4769.0 1994.58  4790.8 1996.15  4812.5 1994.96  4863.8 1997.03
  4879.0 1995.85  4944.8 1995.49  4977.8 1988.57  4983.0 1988.39  4994.0 1982.00
  4994.5 1981.50  5025.2 1982.00  5039.6 1987.37  5049.6 2003.94  5059.6 2006.75
  5089.6 2010.13  5159.6 2012.86  5179.6 2015.55  5249.6 2020.84  5399.6 2024.70
#Mann=6,-1,0
  4477.6    0.07       0  4518.1     0.1       0  4671.8   0.035       0
  4879.0    0.07       0  4994.0    0.05       0  5025.2    0.07       0
Bank Sta=4994,5025.2
Exp/Cntr=0.3,0.1

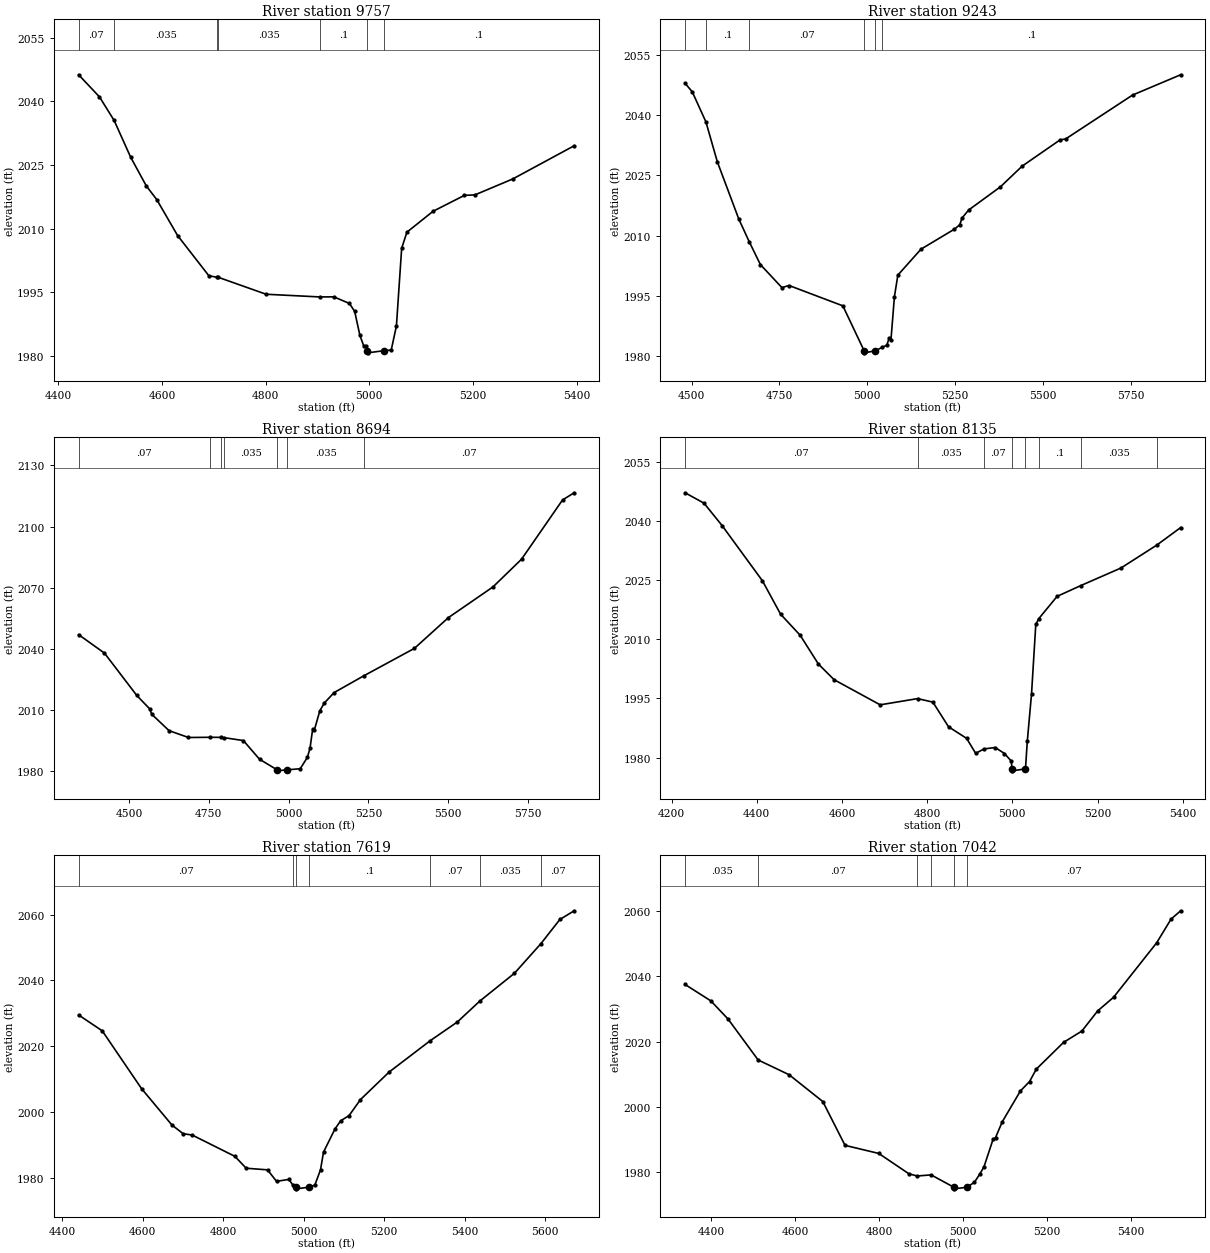
Type RM Length L Ch R = 1,9757,514,514,514
BEGIN DESCRIPTION:
Flat Rock Creek 17.0
END DESCRIPTION:
XS GIS Cut Line= 3
      1802075.00     13928774.99      1802025.00     13928225.00
      1802075.00     13927824.97
#Sta/Elev= 30
  4439.5 2046.28  4479.7 2041.07  4508.0 2035.51  4539.9 2026.84  4570.0 2020.10
  4590.1 2016.88  4630.3 2008.41  4690.5 1998.95  4706.1 1998.58  4708.1 1998.60
  4801.0 1994.58  4904.2 1993.95  4931.5 1993.97  4961.6 1992.41  4971.7 1990.55
  4981.7 1984.93  4989.3 1982.37  4994.3 1982.37  4996.3 1981.28  4996.8 1980.78
  5027.6 1981.28  5042.2 1981.44  5052.2 1987.12  5062.3 2005.39  5072.4 2009.20
  5122.8 2014.12  5183.2 2017.87  5203.4 2017.98  5276.5 2021.74  5394.9 2029.56
#Mann=7,-1,0
  4439.5    0.07       0  4508.0   0.035       0  4706.1    0.07       0
  4708.1   0.035       0  4904.2     0.1       0  4996.3    0.05       0
  5027.6     0.1       0
Bank Sta=4996.3,5027.6
Exp/Cntr=0.3,0.1

Type RM Length L Ch R = 1,9243,549,549,549
BEGIN DESCRIPTION:
Flat Rock Creek 16.0
END DESCRIPTION:
XS GIS Cut Line= 4
      1802375.01     13928774.96      1802475.00     13928275.00
      1802325.00     13927875.00      1802144.41     13927438.54
#Sta/Elev= 30
  4481.6 2047.94  4502.0 2045.81  4540.8 2038.33  4573.3 2028.37  4634.5 2014.07
  4664.1 2008.44  4695.7 2002.77  4756.9 1997.03  4777.3 1997.55  4930.3 1992.48
  4990.9 1981.27  4991.4 1980.77  5022.2 1981.27  5042.5 1982.15  5055.5 1982.70
  5061.8 1984.42  5067.1 1983.99  5076.9 1994.71  5086.7 2000.14  5152.5 2006.60
  5247.8 2011.60  5262.9 2012.70  5269.1 2014.34  5287.8 2016.34  5378.6 2022.15
  5440.3 2027.30  5548.5 2033.86  5563.6 2034.05  5754.1 2045.00  5891.0 2050.06
#Mann=6,-1,0
  4481.6    0.07       0  4540.8     0.1       0  4664.1    0.07       0
  4990.9    0.05       0  5022.2    0.07       0  5042.5     0.1       0
Bank Sta=4990.9,5022.2
Exp/Cntr=0.3,0.1

Type RM Length L Ch R = 1,8694,559,559,559
BEGIN DESCRIPTION:
Flat Rock Creek 15.0
END DESCRIPTION:
XS GIS Cut Line= 3
      1802875.00     13928874.99      1802975.00     13928225.00
      1803375.02     13927424.96
#Sta/Elev= 30
  4342.2 2046.92  4423.1 2037.85  4524.3 2017.06  4564.8 2010.44  4571.1 2007.82
  4625.5 1999.75  4686.2 1996.40  4753.9 1996.50  4787.2 1996.46  4797.7 1996.32
  4858.2 1994.89  4908.8 1985.72  4963.8 1980.52  4964.3 1980.02  4995.4 1980.52
  5036.2 1981.05  5058.5 1986.59  5066.9 1991.07  5075.3 2000.61  5080.9 2000.28
  5097.7 2009.52  5111.6 2013.31  5142.4 2018.46  5235.9 2026.74  5393.9 2040.17
  5500.2 2055.26  5639.9 2070.35  5729.4 2083.96  5857.9 2113.08  5894.3 2116.60
#Mann=7,-1,0
  4342.2    0.07       0  4753.9   0.035       0  4787.2    0.07       0
  4797.7   0.035       0  4963.8    0.05       0  4995.4   0.035       0
  5235.9    0.07       0
Bank Sta=4963.8,4995.4
Exp/Cntr=0.3,0.1

Type RM Length L Ch R = 1,8135,516,516,516
BEGIN DESCRIPTION:
Flat Rock Creek 14.0
END DESCRIPTION:
XS GIS Cut Line= 3
      1803075.01     13928974.98      1803475.00     13928325.00
      1803475.00     13927925.00
#Sta/Elev= 30
  4231.8 2047.20  4276.2 2044.56  4318.7 2038.87  4413.4 2024.85  4456.0 2016.38
  4501.8 2011.06  4544.8 2003.73  4581.5 1999.77  4689.7 1993.39  4777.5 1994.97
  4813.4 1994.08  4850.1 1987.83  4892.6 1984.88  4913.9 1981.08  4933.4 1982.20
  4959.8 1982.56  4981.4 1981.04  4997.5 1979.11  4999.2 1977.14  4999.7 1976.64
  5030.8 1977.14  5035.0 1984.09  5045.0 1996.17  5055.0 2013.80  5062.1 2015.27
  5105.0 2020.91  5160.4 2023.64  5255.0 2028.11  5339.5 2033.96  5395.0 2038.37
#Mann=8,-1,0
  4231.8    0.07       0  4777.5   0.035       0  4933.4    0.07       0
  4999.2    0.05       0  5030.8    0.07       0  5062.1     0.1       0
  5160.4   0.035       0  5339.5    0.07       0
Bank Sta=4999.2,5030.8
Exp/Cntr=0.3,0.1

Type RM Length L Ch R = 1,7619,577,577,577
BEGIN DESCRIPTION:
Flat Rock Creek 13.0
END DESCRIPTION:
XS GIS Cut Line= 3
      1803675.02     13929024.96      1803925.00     13928525.00
      1804375.03     13928024.96
#Sta/Elev= 30
  4440.8 2029.46  4499.5 2024.64  4597.3 2007.03  4672.7 1995.98  4700.7 1993.33
  4723.1 1992.93  4829.3 1986.44  4857.2 1982.83  4910.3 1982.34  4932.7 1978.84
  4963.4 1979.43  4973.8 1977.63  4981.1 1977.06  4981.6 1976.56  5012.9 1977.06
  5027.8 1977.68  5042.0 1982.35  5049.5 1987.75  5077.9 1994.76  5092.1 1997.27
  5113.0 1998.85  5141.4 2003.73  5212.4 2012.08  5314.5 2021.62  5382.1 2027.33
  5437.8 2033.68  5524.1 2042.16  5589.7 2051.15  5636.9 2058.52  5672.5 2061.17
#Mann=7,-1,0
  4440.8    0.07       0  4973.8     0.1       0  4981.1    0.05       0
  5012.9     0.1       0  5314.5    0.07       0  5437.8   0.035       0
  5589.7    0.07       0
Bank Sta=4981.1,5012.9
Exp/Cntr=0.3,0.1

Type RM Length L Ch R = 1,7042,539,539,539
BEGIN DESCRIPTION:
Flat Rock Creek 12.0
END DESCRIPTION:
XS GIS Cut Line= 3
      1804275.01     13929374.96      1804425.00     13928725.00
      1804674.99     13928275.02
#Sta/Elev= 30
  4337.4 2037.47  4398.9 2032.45  4440.0 2026.87  4511.6 2014.36  4585.4 2009.85
  4665.8 2001.64  4718.8 1988.22  4799.2 1985.75  4871.0 1979.53  4890.7 1978.84
  4924.1 1979.18  4978.2 1975.41  4978.7 1974.91  5010.1 1975.41  5027.3 1976.93
  5039.9 1979.35  5050.2 1981.66  5071.9 1990.09  5077.7 1990.57  5093.7 1995.42
  5137.1 2004.88  5158.9 2007.76  5174.9 2011.55  5240.1 2019.76  5283.6 2023.21
  5321.3 2029.38  5359.1 2033.54  5462.0 2050.23  5496.3 2057.48  5519.2 2060.04
#Mann=6,-1,0
  4337.4   0.035       0  4511.6    0.07       0  4890.7     0.1       0
  4924.1    0.07       0  4978.2    0.05       0  5010.1    0.07       0
Bank Sta=4978.2,5010.1
Exp/Cntr=0.3,0.1