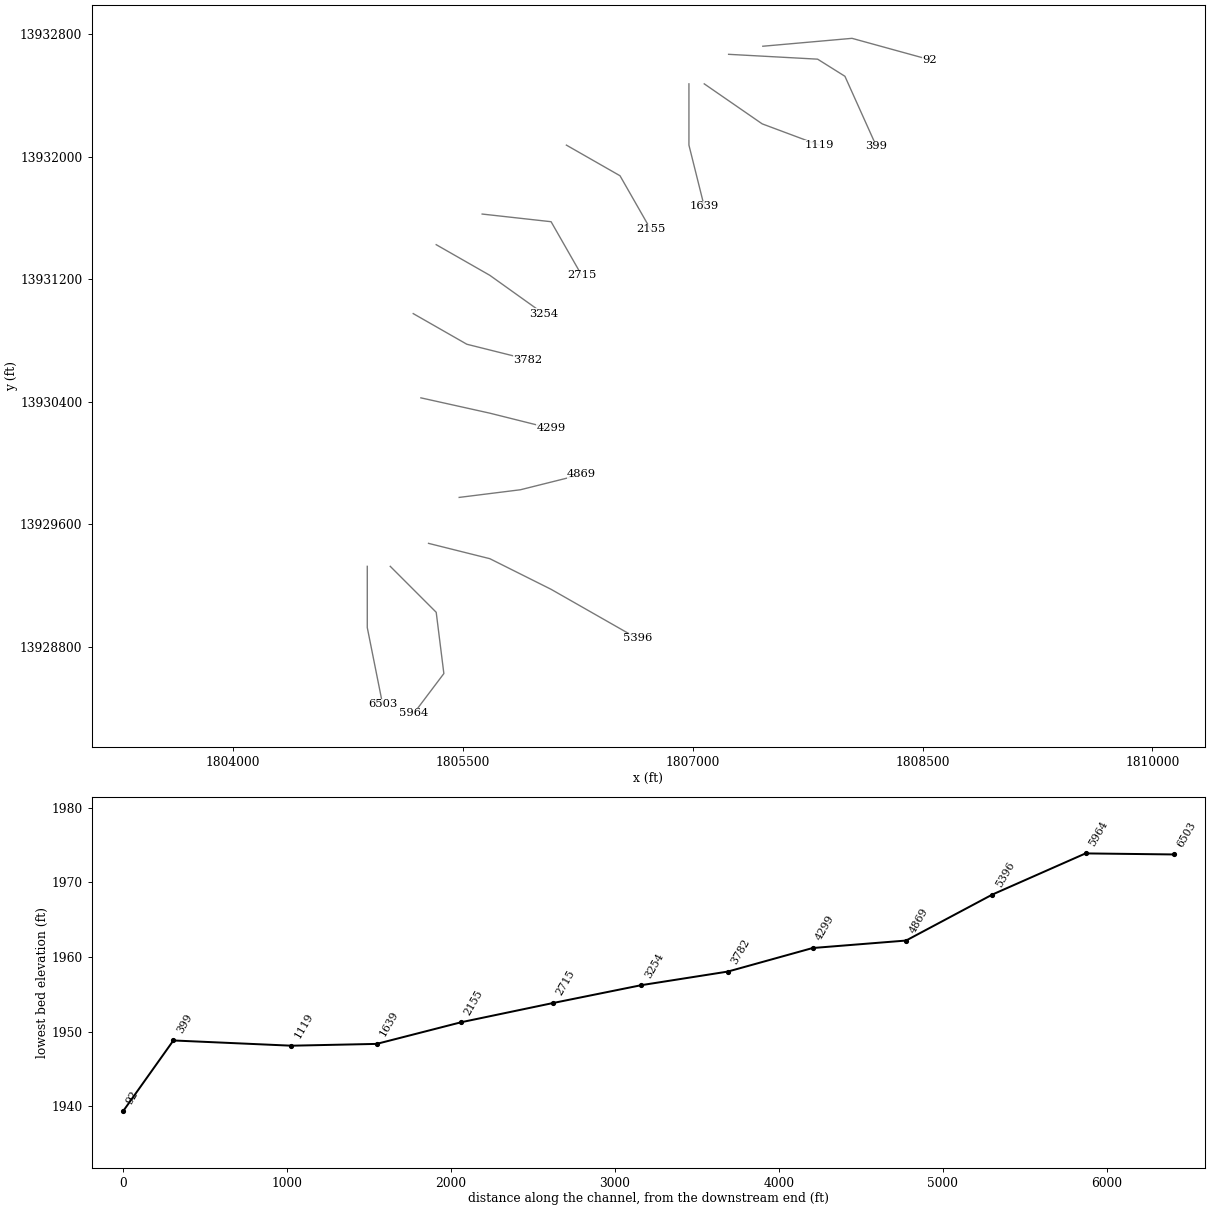
HEC-RAS study Flat Rock Creek.prj: Flat Rock Creek Base Level Engineering

--- Flat Rock Creek.g01 (geometry) --- (continued)

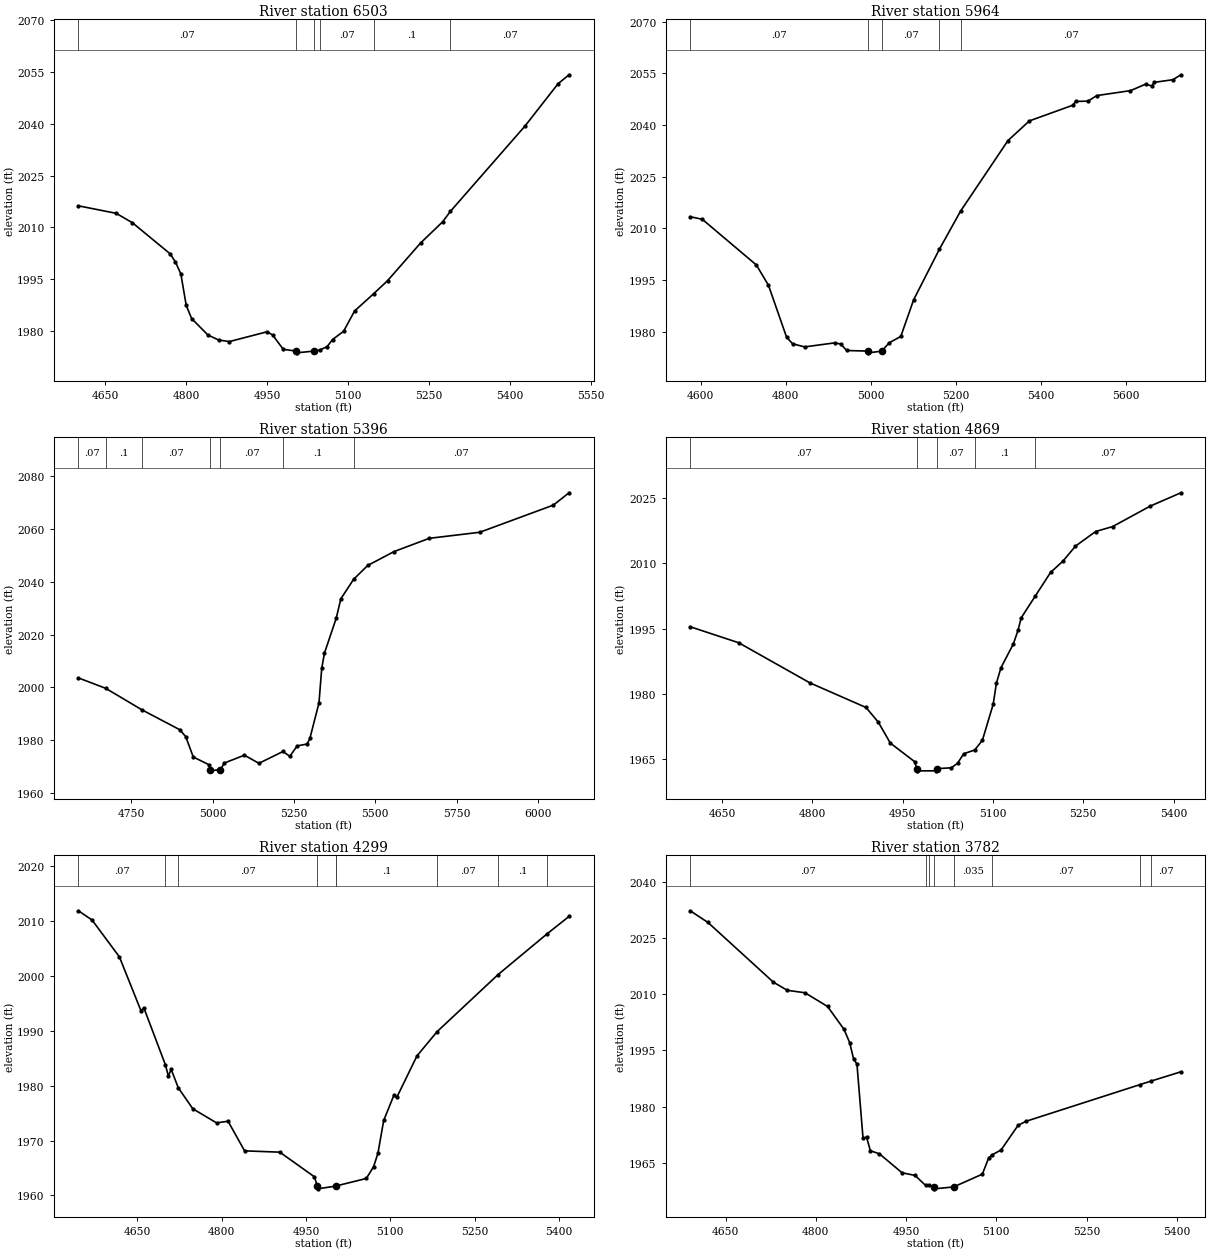
Type RM Length L Ch R = 1,6503,539,539,539
BEGIN DESCRIPTION:
Flat Rock Creek 11.0
END DESCRIPTION:
XS GIS Cut Line= 3
      1804875.00     13929324.98      1804875.00     13928925.00
      1804975.00     13928424.98
#Sta/Elev= 30
  4600.2 2016.27  4670.2 2014.10  4700.2 2011.40  4770.2 2002.40  4780.2 2000.02
  4790.2 1996.57  4800.2 1987.44  4810.2 1983.65  4840.2 1978.91  4860.2 1977.43
  4880.2 1976.98  4950.2 1979.82  4960.2 1978.91  4980.2 1974.73  5004.6 1974.22
  5005.1 1973.72  5036.5 1974.22  5047.7 1974.52  5061.4 1975.51  5071.6 1977.57
  5092.0 1979.96  5112.4 1985.84  5147.7 1990.82  5173.5 1994.60  5234.7 2005.50
  5275.5 2011.61  5290.0 2014.65  5428.5 2039.38  5489.7 2051.60  5510.1 2054.20
#Mann=6,-1,0
  4600.2    0.07       0  5004.6    0.05       0  5036.5    0.07       0
  5047.7    0.07       0  5147.7     0.1       0  5290.0    0.07       0
Bank Sta=5004.6,5036.5
Exp/Cntr=0.3,0.1

Type RM Length L Ch R = 1,5964,568,568,568
BEGIN DESCRIPTION:
Flat Rock Creek 10.0
END DESCRIPTION:
XS GIS Cut Line= 4
      1805025.02     13929324.98      1805325.00     13929025.00
      1805375.00     13928625.00      1805178.88     13928365.03
#Sta/Elev= 30
  4575.4 2013.36  4603.7 2012.63  4730.9 1999.35  4759.2 1993.49  4801.7 1978.45
  4815.8 1976.50  4844.1 1975.58  4914.8 1976.75  4928.9 1976.43  4943.1 1974.54
  4993.8 1974.36  4994.3 1973.86  5025.7 1974.36  5042.5 1976.74  5070.2 1978.62
  5100.4 1989.25  5160.8 2003.90  5210.8 2015.01  5322.1 2035.47  5372.5 2041.18
  5474.6 2045.73  5480.8 2046.82  5510.0 2046.91  5530.8 2048.52  5609.9 2049.96
  5645.3 2051.82  5659.8 2051.33  5666.1 2052.37  5709.8 2053.13  5728.4 2054.56
#Mann=5,-1,0
  4575.4    0.07       0  4993.8    0.05       0  5025.7    0.07       0
  5160.8     0.1       0  5210.8    0.07       0
Bank Sta=4993.8,5025.7
Exp/Cntr=0.3,0.1

Type RM Length L Ch R = 1,5396,527,527,527
BEGIN DESCRIPTION:
Flat Rock Creek 9.0
END DESCRIPTION:
XS GIS Cut Line= 4
      1805274.96     13929475.01      1805675.00     13929375.00
      1806075.00     13929175.00      1806638.28     13928853.99
#Sta/Elev= 30
  4587.4 2003.58  4671.3 1999.64  4782.7 1991.48  4899.3 1983.92  4917.3 1981.31
  4940.5 1973.60  4989.4 1970.64  4992.2 1968.86  4992.7 1968.36  5024.1 1968.86
  5036.1 1971.33  5097.6 1974.29  5142.3 1971.21  5216.1 1975.69  5237.3 1973.85
  5259.7 1977.82  5290.4 1978.51  5298.8 1980.62  5326.8 1994.12  5335.2 2007.19
  5343.6 2012.97  5379.9 2026.23  5393.9 2033.54  5433.3 2040.96  5476.5 2046.19
  5557.2 2051.44  5665.7 2056.48  5820.8 2058.77  6047.0 2069.06  6095.3 2073.74
#Mann=7,-1,0
  4587.4    0.07       0  4671.3     0.1       0  4782.7    0.07       0
  4992.2    0.05       0  5024.1    0.07       0  5216.1     0.1       0
  5433.3    0.07       0
Bank Sta=4992.2,5024.1
Exp/Cntr=0.3,0.1

Type RM Length L Ch R = 1,4869,570,570,570
BEGIN DESCRIPTION:
Flat Rock Creek 8.0
END DESCRIPTION:
XS GIS Cut Line= 3
      1805475.02     13929775.00      1805875.00     13929825.00
      1806274.99     13929925.00
#Sta/Elev= 30
  4596.8 1995.41  4677.4 1991.72  4795.8 1982.47  4889.0 1976.80  4909.2 1973.45
  4929.4 1968.59  4969.7 1964.32  4973.4 1962.70  4974.0 1962.20  5005.7 1962.20
  5006.2 1962.70  5030.8 1962.90  5041.1 1963.96  5051.4 1966.15  5069.6 1967.00
  5082.4 1969.26  5100.4 1977.61  5105.6 1982.40  5113.3 1986.00  5133.9 1991.48
  5141.6 1994.62  5146.8 1997.46  5169.9 2002.42  5195.7 2007.94  5216.4 2010.56
  5237.0 2013.99  5270.5 2017.36  5298.8 2018.50  5360.7 2023.18  5412.2 2026.29
#Mann=5,-1,0
  4596.8    0.07       0  4973.4    0.05       0  5006.2    0.07       0
  5069.6     0.1       0  5169.9    0.07       0
Bank Sta=4973.4,5006.2
Exp/Cntr=0.3,0.1

Type RM Length L Ch R = 1,4299,517,517,517
BEGIN DESCRIPTION:
Flat Rock Creek 7.0
END DESCRIPTION:
XS GIS Cut Line= 3
      1805224.99     13930425.00      1805675.00     13930325.00
      1806075.00     13930225.00
#Sta/Elev= 30
  4544.8 2011.92  4569.1 2010.24  4617.8 2003.51  4656.2 1993.68  4661.3 1994.22
  4699.7 1983.82  4704.9 1981.78  4710.0 1982.98  4722.5 1979.65  4748.4 1975.81
  4790.7 1973.23  4811.2 1973.53  4840.6 1968.13  4903.3 1967.89  4964.8 1963.40
  4970.1 1961.70  4970.7 1961.20  5003.0 1961.70  5004.1 1961.74  5057.3 1963.09
  5070.2 1965.24  5077.9 1967.66  5088.2 1973.67  5106.3 1978.26  5111.4 1977.87
  5147.5 1985.46  5183.4 1989.89  5291.9 2000.29  5379.2 2007.73  5418.1 2010.89
#Mann=9,-1,0
  4544.8    0.07       0  4699.7     0.1       0  4722.5    0.07       0
  4970.1    0.05       0  5003.0    0.07       0  5004.1     0.1       0
  5183.4    0.07       0  5291.9     0.1       0  5379.2    0.07       0
Bank Sta=4970.1,5003
Exp/Cntr=0.3,0.1

Type RM Length L Ch R = 1,3782,528,528,528
BEGIN DESCRIPTION:
Flat Rock Creek 6.0
END DESCRIPTION:
XS GIS Cut Line= 3
      1805175.02     13930974.99      1805525.00     13930775.00
      1805925.00     13930675.00
#Sta/Elev= 30
  4591.3 2032.22  4620.8 2029.10  4729.5 2013.18  4752.5 2011.01  4782.0 2010.35
  4819.5 2006.70  4846.8 2000.62  4856.2 1997.08  4862.7 1992.75  4868.4 1991.30
  4878.5 1971.51  4884.3 1971.85  4890.7 1968.22  4905.8 1967.38  4943.3 1962.34
  4964.9 1961.63  4982.4 1958.97  4988.1 1959.00  4996.0 1958.55  4996.5 1958.05
  5028.9 1958.55  5076.8 1961.97  5087.2 1966.27  5093.1 1967.14  5107.8 1968.40
  5136.1 1974.98  5149.0 1976.05  5339.3 1985.88  5357.3 1986.80  5406.7 1989.27
#Mann=8,-1,0
  4591.3    0.07       0  4982.4     0.1       0  4988.1   0.035       0
  4996.0   0.035       0  5028.9   0.035       0  5093.1    0.07       0
  5339.3     0.1       0  5357.3    0.07       0
Bank Sta=4996,5028.9
Exp/Cntr=0.3,0.1

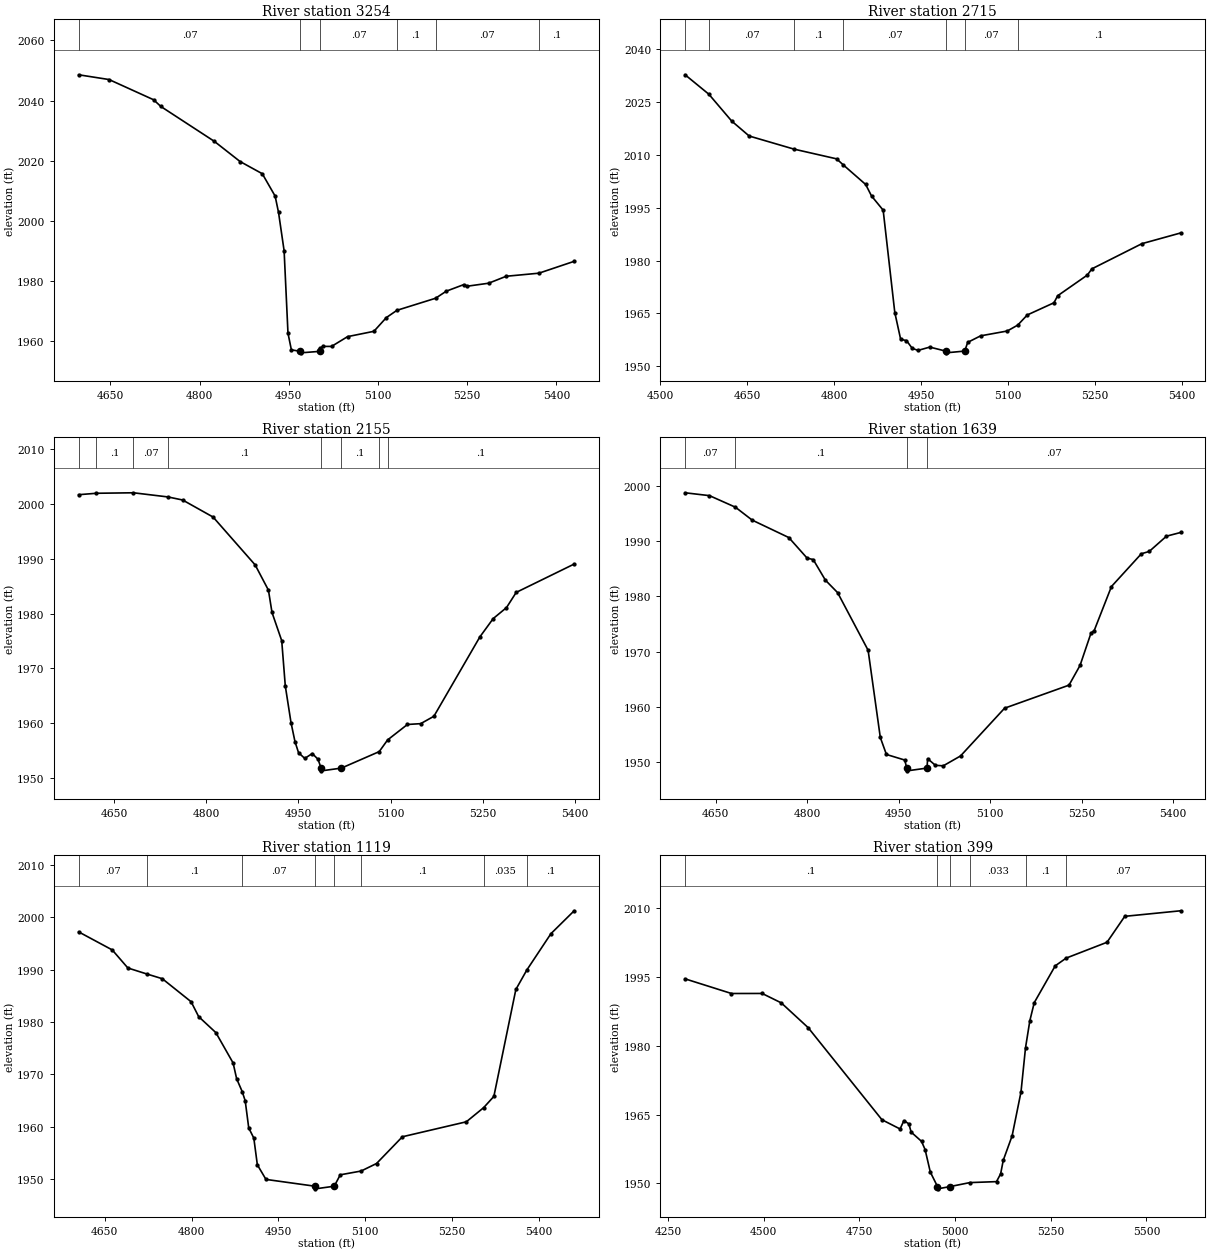
Type RM Length L Ch R = 1,3254,539,539,539
BEGIN DESCRIPTION:
Flat Rock Creek 5.0
END DESCRIPTION:
XS GIS Cut Line= 3
      1805325.02     13931424.99      1805675.00     13931225.00
      1806024.99     13930975.01
#Sta/Elev= 30
  4596.7 2048.57  4647.8 2046.99  4722.7 2040.28  4734.9 2038.05  4824.9 2026.46
  4868.1 2019.77  4905.5 2015.71  4927.1 2008.28  4932.8 2002.87  4942.2 1990.13
  4948.7 1962.76  4954.4 1957.22  4969.7 1956.73  4970.2 1956.23  5002.6 1956.73
  5002.9 1957.76  5007.2 1958.37  5021.9 1958.36  5048.9 1961.61  5093.2 1963.38
  5114.1 1967.94  5131.9 1970.35  5196.9 1974.36  5214.9 1976.71  5244.3 1978.89
  5250.5 1978.37  5286.1 1979.35  5315.6 1981.66  5370.6 1982.68  5429.9 1986.62
#Mann=6,-1,0
  4596.7    0.07       0  4969.7    0.05       0  5002.6    0.07       0
  5131.9     0.1       0  5196.9    0.07       0  5370.6     0.1       0
Bank Sta=4969.7,5002.6
Exp/Cntr=0.3,0.1

Type RM Length L Ch R = 1,2715,560,560,560
BEGIN DESCRIPTION:
Flat Rock Creek 4.0
END DESCRIPTION:
XS GIS Cut Line= 3
      1805624.98     13931625.00      1806075.00     13931575.00
      1806275.00     13931225.00
#Sta/Elev= 30
  4542.6 2032.70  4583.6 2027.19  4623.1 2019.57  4653.3 2015.33  4730.8 2011.61
  4804.2 2008.86  4816.0 2007.11  4854.5 2001.59  4864.6 1998.33  4884.7 1994.30
  4904.8 1965.27  4914.9 1957.68  4925.0 1957.31  4935.0 1955.10  4945.1 1954.54
  4965.2 1955.47  4992.6 1954.34  4993.2 1953.84  5025.6 1954.34  5030.7 1956.81
  5053.0 1958.66  5099.0 1960.03  5117.1 1961.70  5133.6 1964.58  5179.7 1968.04
  5186.1 1970.03  5237.3 1975.89  5245.2 1977.66  5331.6 1984.80  5398.5 1987.84
#Mann=7,-1,0
  4542.6     0.1       0  4583.6    0.07       0  4730.8     0.1       0
  4816.0    0.07       0  4992.6    0.05       0  5025.6    0.07       0
  5117.1     0.1       0
Bank Sta=4992.6,5025.6
Exp/Cntr=0.3,0.1

Type RM Length L Ch R = 1,2155,516,516,516
BEGIN DESCRIPTION:
Flat Rock Creek 3.0
END DESCRIPTION:
XS GIS Cut Line= 3
      1806174.99     13932075.01      1806525.00     13931875.00
      1806724.98     13931525.03
#Sta/Elev= 30
  4592.3 2001.72  4621.3 2001.98  4681.5 2002.07  4737.6 2001.31  4761.5 2000.75
  4811.1 1997.63  4879.5 1988.89  4901.1 1984.28  4906.9 1980.20  4922.7 1975.05
  4928.5 1966.80  4937.8 1960.09  4944.3 1956.60  4950.1 1954.58  4960.2 1953.54
  4972.4 1954.43  4981.7 1953.39  4986.8 1951.77  4987.4 1951.27  5019.8 1951.77
  5081.3 1954.78  5095.0 1956.92  5127.2 1959.74  5148.8 1959.89  5170.3 1961.24
  5245.2 1975.76  5266.8 1979.09  5288.4 1981.09  5304.2 1983.87  5398.5 1989.05
#Mann=8,-1,0
  4592.3    0.07       0  4621.3     0.1       0  4681.5    0.07       0
  4737.6     0.1       0  4986.8    0.05       0  5019.8     0.1       0
  5081.3    0.07       0  5095.0     0.1       0
Bank Sta=4986.8,5019.8
Exp/Cntr=0.3,0.1

Type RM Length L Ch R = 1,1639,520,520,520
BEGIN DESCRIPTION:
Flat Rock Creek 2.0
END DESCRIPTION:
XS GIS Cut Line= 3
      1806975.00     13932474.98      1806975.00     13932075.00
      1807075.00     13931674.99
#Sta/Elev= 30
  4600.0 1998.80  4640.0 1998.28  4682.4 1996.19  4710.0 1993.84  4770.0 1990.68
  4800.0 1986.95  4810.0 1986.69  4830.0 1982.95  4850.0 1980.69  4900.0 1970.24
  4920.0 1954.42  4930.0 1951.34  4960.0 1950.33  4963.4 1948.87  4964.0 1948.37
  4996.6 1948.87  4997.5 1950.58  5010.3 1949.37  5023.2 1949.28  5051.5 1951.07
  5123.7 1959.73  5229.3 1963.91  5247.4 1967.49  5265.4 1973.36  5270.6 1973.81
  5298.9 1981.80  5347.9 1987.74  5360.8 1988.16  5389.1 1990.93  5412.3 1991.60
#Mann=4,-1,0
  4600.0    0.07       0  4682.4     0.1       0  4963.4    0.05       0
  4996.6    0.07       0
Bank Sta=4963.4,4996.6
Exp/Cntr=0.3,0.1

Type RM Length L Ch R = 1,1119,720,720,720
BEGIN DESCRIPTION:
Flat Rock Creek 1.0
END DESCRIPTION:
XS GIS Cut Line= 3
      1807075.03     13932474.98      1807453.18     13932213.83
      1807825.04     13932074.98
#Sta/Elev= 30
  4604.7 1997.23  4662.8 1993.78  4689.8 1990.33  4722.1 1989.20  4749.3 1988.28
  4799.1 1983.88  4812.2 1981.03  4841.9 1977.98  4871.7 1972.18  4877.8 1969.17
  4887.4 1966.71  4892.6 1964.96  4898.7 1959.77  4907.5 1957.82  4913.6 1952.72
  4928.5 1949.93  5013.3 1948.63  5013.9 1948.13  5046.5 1948.63  5056.9 1950.81
  5092.9 1951.53  5119.6 1952.97  5164.3 1958.08  5274.8 1960.94  5304.8 1963.65
  5322.4 1965.79  5360.4 1986.22  5379.3 1989.93  5421.0 1996.88  5461.2 2001.26
#Mann=8,-1,0
  4604.7    0.07       0  4722.1     0.1       0  4887.4    0.07       0
  5013.3    0.05       0  5046.5    0.07       0  5092.9     0.1       0
  5304.8   0.035       0  5379.3     0.1       0
Bank Sta=5013.3,5046.5
Exp/Cntr=0.3,0.1

Type RM Length L Ch R = 1,399,307,307,307
BEGIN DESCRIPTION:
Flat Rock Creek 1.1
END DESCRIPTION:
XS GIS Cut Line= 4
      1807234.02     13932667.83      1807815.09     13932636.21
      1807993.40     13932524.44      1808199.55     13932066.03
#Sta/Elev= 30
  4294.4 1994.57  4415.6 1991.38  4495.7 1991.39  4545.7 1989.34  4615.9 1983.95
  4808.8 1963.88  4856.2 1961.87  4866.2 1963.69  4879.2 1962.98  4885.1 1961.19
  4912.2 1959.18  4921.6 1957.38  4935.2 1952.49  4954.0 1949.33  4954.6 1948.83
  4987.3 1949.33  5038.5 1950.19  5108.2 1950.40  5119.0 1952.10  5125.9 1955.06
  5149.0 1960.37  5172.2 1969.93  5184.0 1979.55  5195.4 1985.49  5206.8 1989.38
  5261.6 1997.40  5290.2 1999.09  5397.0 2002.54  5443.4 2008.19  5589.4 2009.40
#Mann=6,-1,0
  4294.4     0.1       0  4954.0    0.05       0  4987.3     0.1       0
  5038.5   0.033       0  5184.0     0.1       0  5290.2    0.07       0
Bank Sta=4954,4987.3
Exp/Cntr=0.3,0.1

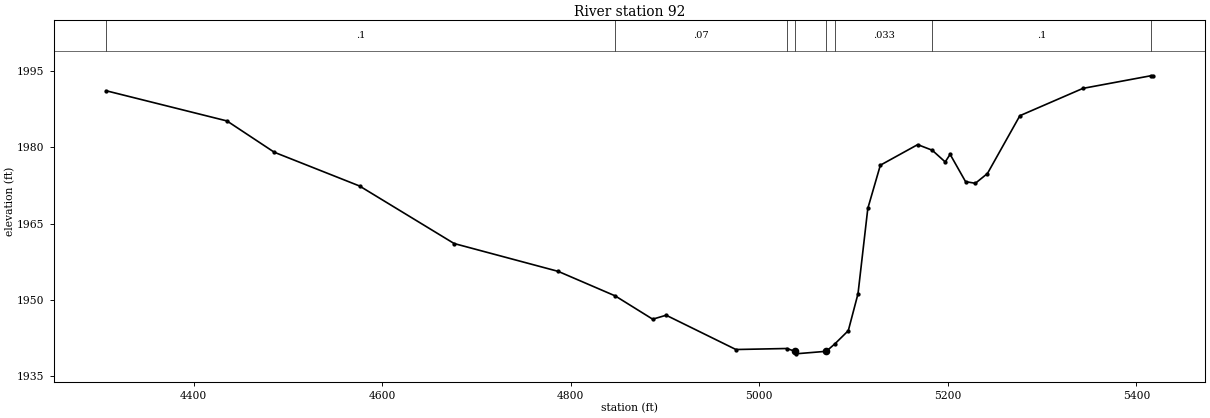
Type RM Length L Ch R = 1,92,0,0,0
BEGIN DESCRIPTION:
Flat Rock Creek 0.0
END DESCRIPTION:
XS GIS Cut Line= 3
      1807457.38     13932720.57      1808039.69     13932772.18
      1808546.75     13932632.65
#Sta/Elev= 30
  4307.2 1991.14  4435.3 1985.20  4485.5 1979.04  4575.9 1972.40  4676.3 1961.07
  4786.7 1955.59  4847.1 1950.77  4886.9 1946.18  4901.2 1946.96  4975.2 1940.21
  5029.2 1940.41  5037.8 1939.86  5038.4 1939.36  5071.1 1939.86  5080.3 1941.35
  5094.4 1943.92  5104.7 1951.19  5115.1 1967.98  5128.4 1976.49  5168.0 1980.54
  5183.4 1979.44  5197.2 1977.13  5202.4 1978.63  5218.8 1973.25  5229.2 1972.93
  5242.0 1974.85  5276.4 1986.23  5343.3 1991.61  5415.2 1994.09  5417.7 1994.09
#Mann=8,-1,0
  4307.2     0.1       0  4847.1    0.07       0  5029.2     0.1       0
  5037.8    0.05       0  5071.1     0.1       0  5080.3   0.033       0
  5183.4     0.1       0  5415.2    0.07       0
Bank Sta=5037.8,5071.1
Exp/Cntr=0.3,0.1

Chan Stop Cuts=-1