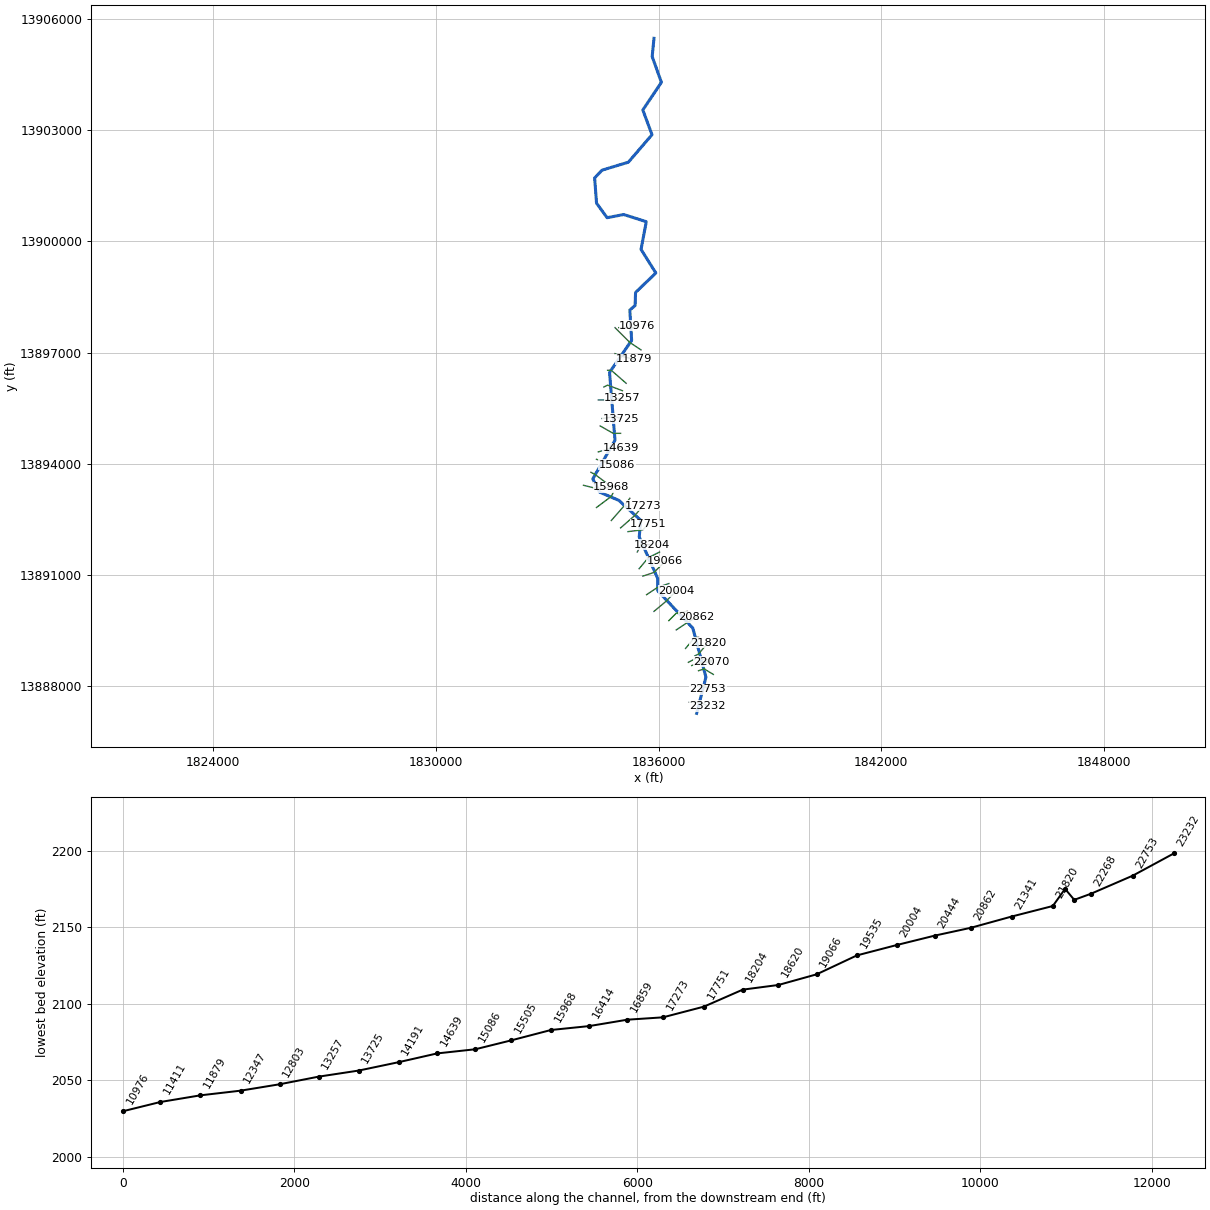
--- Frank Baker Creek.prj (project) ---

Proj Title=Frank Baker Creek Base Level Engineering
Current Plan=p01
Default Exp/Contr=0.3,0.1
English Units
Geom File=g01
Flow File=f01
Plan File=p01
Y Axis Title=Elevation
X Axis Title(PF)=Main Channel Distance
X Axis Title(XS)=Station
BEGIN DESCRIPTION:
Frank Baker Creek
END DESCRIPTION:
DSS Export Rating Curves= 0
DSS Export Rating Curve Sorted= 0
DSS Export Volume Flow Curves= 0
DXF OffsetX= 0
DXF OffsetY= 0
DXF ScaleX= 1
DXF ScaleY= 10

--- Frank Baker Creek.p01 (plan) ---

Plan Title=Multiple Run
Short Identifier=Multiple
Geom File=g01
Flow File=f01
Subcritical Flow
K Sum by GR= 0
Std Step Tol= 0.01
Critical Tol= 0.01
Num of Std Step Trials= 20
Max Error Tol= 0.3
Flow Tol Ratio= 0.001
Split Flow NTrial= 30
Split Flow Tol= 0.02
Split Flow Ratio= 0.02
Log Output Level= 0
Friction Slope Method= 1
Unsteady Friction Slope Method= 2
Unsteady Bridges Friction Slope Method= 1
Parabolic Critical Depth
Global Vel Dist=  1 , 1 , 1
Global Log Level= 0
CheckData=True
Encroach Param= -1, 0, 0, 0
BEGIN DESCRIPTION:
Multiple Run
END DESCRIPTION:

--- Frank Baker Creek.f01 (steady flow) ---

Flow Title=Multiple
Number of Profiles=7
Profile Names=10-year,25-year,50-year,1pct_min,100-year,1pct_plu,500-year
River Rch & RM= Frank Baker Cree,Reach-1,23232
     227     349     456     289     577    1152     911
River Rch & RM= Frank Baker Cree,Reach-1,22268
    1367    2381    3365    2298    4585    9149    8420
River Rch & RM= Frank Baker Cree,Reach-1,17751
    1883    3315    4717    3236    6457   12884   11978
River Rch & RM= Frank Baker Cree,Reach-1,8763
    2473    4409    6325    4371    8721   17401   16416
River Rch & RM= Frank Baker Cree,Reach-1,4643
    2644    4725    6789    4698    9373   18702   17689
Boundary for River Rch & Prof#=Frank Baker Cree,Reach-1,1
Up Type=0
Dn Type=3
Dn Slope=0.005
Boundary for River Rch & Prof#=Frank Baker Cree,Reach-1,2
Up Type=0
Dn Type=3
Dn Slope=0.005
Boundary for River Rch & Prof#=Frank Baker Cree,Reach-1,3
Up Type=0
Dn Type=3
Dn Slope=0.005
Boundary for River Rch & Prof#=Frank Baker Cree,Reach-1,4
Up Type=0
Dn Type=3
Dn Slope=0.005
Boundary for River Rch & Prof#=Frank Baker Cree,Reach-1,5
Up Type=0
Dn Type=3
Dn Slope=0.005
Boundary for River Rch & Prof#=Frank Baker Cree,Reach-1,6
Up Type=0
Dn Type=3
Dn Slope=0.005
Boundary for River Rch & Prof#=Frank Baker Cree,Reach-1,7
Up Type=0
Dn Type=3
Dn Slope=0.005

--- Frank Baker Creek.g01 (geometry) ---

Geom Title=Existing Conditions
Program Version=4.10

River Reach=Frank Baker Cree,Reach-1
Reach XY= 30
        1837025.       13887275.       1837275.2     13888250.08
      1836921.46     13889573.54      1835978.82     13890576.58
      1835972.86     13890919.03      1835477.16     13892030.98
      1835517.18     13892481.19      1834931.06     13893016.86
      1834411.43     13893238.47      1834224.89      13893595.1
      1834824.45     13894638.97      1834677.35     13896469.48
      1835272.82     13897330.45      1835224.46     13898150.12
      1835367.02     13898271.65      1835378.54     13898623.53
      1835925.49     13899147.77       1835526.2      13899784.6
      1835667.19     13900531.19      1835059.61     13900724.91
      1834611.76     13900638.59      1834327.36     13901030.52
      1834275.67     13901711.09      1834476.58     13901921.18
        1835185.     13902135.63      1835821.47     13902876.46
      1835574.57     13903543.33      1836074.46     13904288.97
      1835826.21     13904984.59        1835875.       13905475.

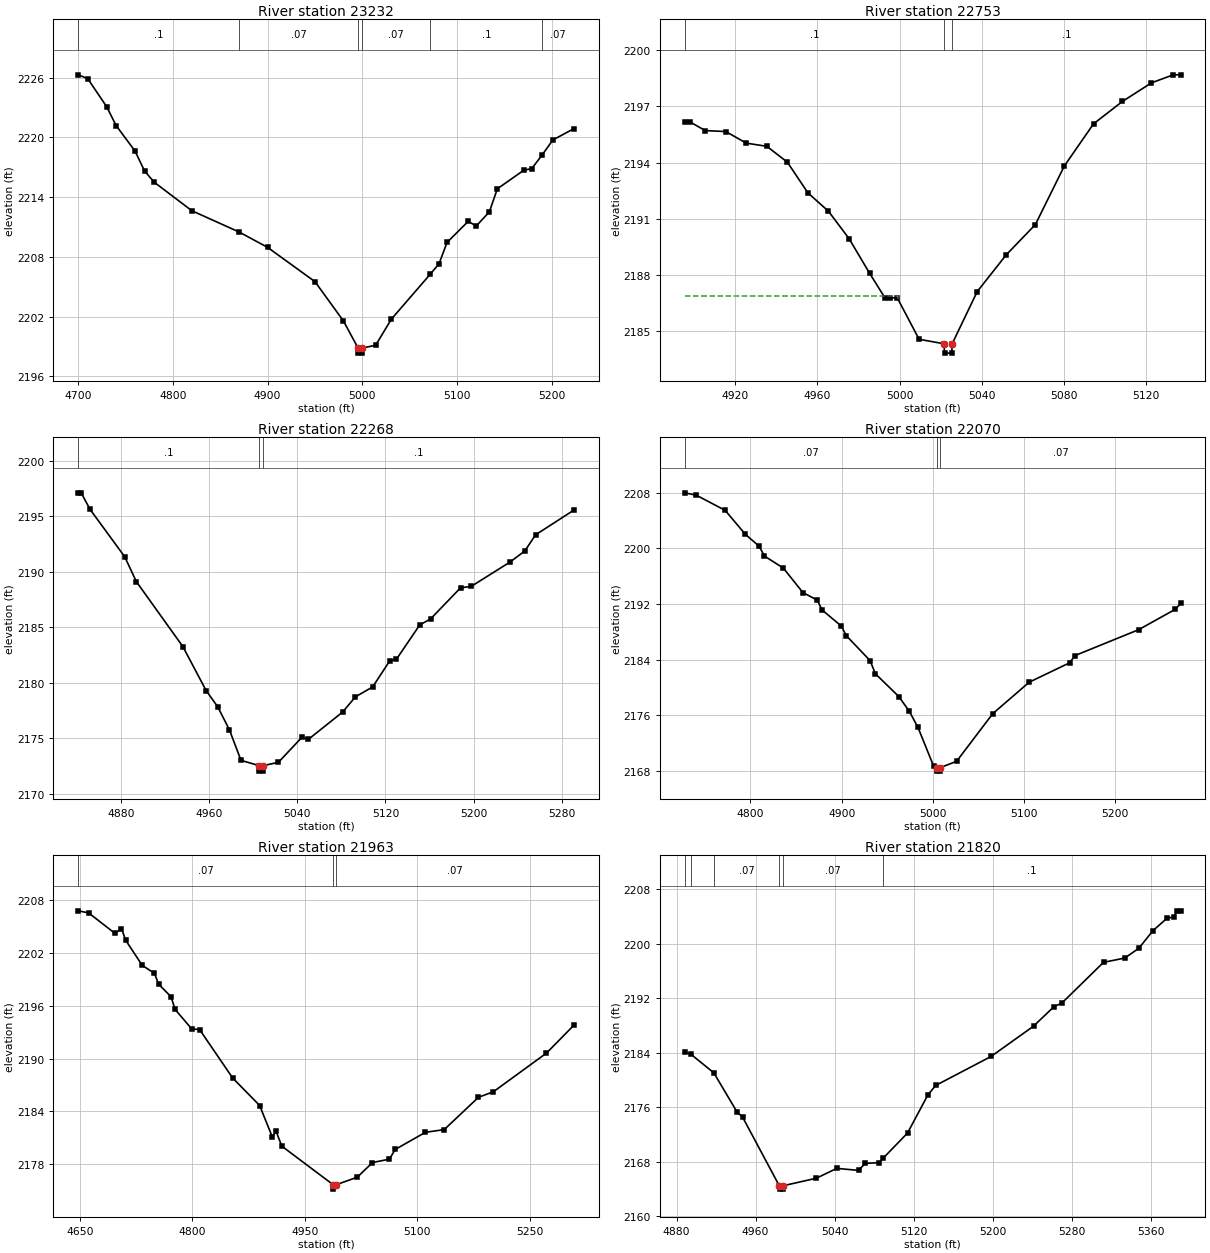
Type RM Length L Ch R = 1 ,23232   ,479,479,479
BEGIN DESCRIPTION:
Frank Baker Creek 51.0
END DESCRIPTION:
XS GIS Cut Line= 3
      1836825.02       13887575.        1837125.       13887575.
      1837325.01     13887474.99
#Sta/Elev= 30
  4700.1 2226.27  4710.1 2225.89  4730.1 2223.08  4740.1 2221.18  4760.1 2218.62
  4770.1 2216.63  4780.1 2215.51  4820.1 2212.63  4870.1 2210.49  4900.1 2208.95
  4950.1 2205.51  4980.1 2201.57  4995.6 2198.84  4995.8 2198.34  4999.3 2198.34
  4999.6 2198.84  5014.1 2199.13  5030.8 2201.76  5071.6 2206.24  5081.1 2207.32
  5089.5 2209.45  5111.9 2211.57  5120.3 2211.09  5134.2 2212.52  5142.6 2214.83
  5170.6  2216.7    5179 2216.86  5190.2 2218.27  5201.3 2219.74  5223.7 2220.88
#Mann= 6 ,-1 , 0
  4700.1      .1       0  4870.1     .07       0  4995.6     .05       0
  4999.6     .07       0  5071.6      .1       0  5190.2     .07       0
Bank Sta=4995.6,4999.6
XS Rating Curve= 0 ,0
Exp/Cntr=0.3,0.1

Type RM Length L Ch R = 1 ,22753   ,485,485,485
BEGIN DESCRIPTION:
Frank Baker Creek 50.0
END DESCRIPTION:
XS GIS Cut Line= 3
      1837125.04       13888025.        1837225.       13888025.
      1837325.01     13887924.99
#Sta/Elev= 28
  4895.4 2196.18  4897.9 2196.18  4905.4 2195.71  4915.4 2195.66  4925.4 2195.04
  4935.4 2194.87  4945.4 2194.02  4955.4 2192.38  4965.4  2191.4  4975.4 2189.94
  4985.4 2188.09  4992.9 2186.77  4995.4 2186.77  4998.9 2186.77  5009.5 2184.56
  5021.6 2184.32  5021.9 2183.82  5025.4 2183.82  5025.6 2184.32  5037.8 2187.11
  5051.9 2189.07  5066.1 2190.69  5080.2 2193.82  5094.4 2196.07  5108.5 2197.27
  5122.6 2198.26  5133.2 2198.69  5136.8 2198.69
#Mann= 3 ,-1 , 0
  4895.4      .1       0  5021.6     .05       0  5025.6      .1       0
#XS Ineff= 2 , 0
         4999.06 2186.87
Permanent Ineff=
       F       F
Bank Sta=5021.6,5025.6
XS Rating Curve= 0 ,0
Exp/Cntr=0.3,0.1

Type RM Length L Ch R = 1 ,22268   ,198,198,198
BEGIN DESCRIPTION:
Frank Baker Creek 49.0
END DESCRIPTION:
XS GIS Cut Line= 3
      1837074.97     13888424.99        1837225.       13888475.
      1837475.01     13888324.99
#Sta/Elev= 30
  4841.4  2197.1  4844.1  2197.1    4852 2195.63  4883.6 2191.34  4894.1 2189.11
  4936.3 2183.26  4957.4  2179.3  4967.9 2177.84  4978.5 2175.77    4989 2173.02
  5005.3 2172.55  5005.6 2172.05  5009.1 2172.05  5009.3 2172.55  5022.9 2172.84
  5044.2 2175.09  5050.1 2174.91  5081.2 2177.37  5092.8 2178.74  5108.4 2179.63
  5123.9 2181.98  5129.8  2182.1  5151.1 2185.21  5160.9 2185.75  5188.1 2188.55
  5197.8 2188.68  5232.8 2190.86  5246.4 2191.87  5256.1 2193.32  5291.1 2195.56
#Mann= 3 ,-1 , 0
  4841.4      .1       0  5005.3     .05       0  5009.3      .1       0
Bank Sta=5005.3,5009.3
XS Rating Curve= 0 ,0
Exp/Cntr=0.3,0.1

Type RM Length L Ch R = 1 ,22070   ,107,107,107
BEGIN DESCRIPTION:
Mapping XS ae9ff410
END DESCRIPTION:
XS GIS Cut Line= 3
      1836891.82     13888564.88      1837170.88     13888656.03
      1837420.89      13888663.8
#Sta/Elev= 30
  4727.9 2207.99  4740.5 2207.66  4772.3 2205.47  4794.4 2202.03  4809.5 2200.32
  4815.4  2198.9  4836.1 2197.17  4857.5 2193.66  4873.3 2192.57  4878.5 2191.16
  4899.6 2188.85  4905.1 2187.46  4931.1 2183.89    4937 2181.99  4962.7 2178.71
  4974.2 2176.59  4983.7 2174.27  5000.8 2168.72    5004  2168.5  5004.3    2168
  5007.8    2168    5008  2168.5    5026 2169.41  5065.6 2176.25  5105.6 2180.78
    5150 2183.57  5155.7  2184.6  5225.7 2188.33  5265.7 2191.25  5271.6 2192.09
#Mann= 3 ,-1 , 0
  4727.9     .07       0    5004     .05       0    5008     .07       0
Bank Sta=5004,5008
XS Rating Curve= 0 ,0
Exp/Cntr=0.3,0.1

Type RM Length L Ch R = 1 ,21963   ,143,143,143
BEGIN DESCRIPTION:
Mapping XS f1dcaaec
END DESCRIPTION:
XS GIS Cut Line= 3
      1836801.64     13888651.53       1837011.7     13888763.13
      1837431.61     13888707.02
#Sta/Elev= 30
  4647.8 2206.82  4661.6 2206.59  4696.9 2204.25  4705.5 2204.81  4711.2 2203.46
  4733.2 2200.62  4749.5 2199.71  4755.1 2198.47  4771.5 2197.06  4777.1  2195.6
  4799.1  2193.4  4809.8 2193.31  4853.7 2187.82  4889.8 2184.68  4906.7  2181.1
  4911.7 2181.75  4919.3 2180.06  4987.9 2175.67  4988.1 2175.17  4991.9 2175.67
  5020.1 2176.53  5040.3 2178.19  5062.9 2178.58  5070.6 2179.68  5110.9 2181.63
    5136 2181.94  5181.6 2185.61  5201.7 2186.25  5272.4 2190.64  5309.3 2193.84
#Mann= 3 ,-1 , 0
  4647.8     .07       0  4987.9     .05       0  4991.9     .07       0
Bank Sta=4987.9,4991.9
XS Rating Curve= 0 ,0
Exp/Cntr=0.3,0.1

Type RM Length L Ch R = 1 ,21820   ,479,479,479
BEGIN DESCRIPTION:
Frank Baker Creek 48.0
END DESCRIPTION:
XS GIS Cut Line= 3
        1836975.       13888825.        1837075.       13888875.
      1837324.99     13889174.99
#Sta/Elev= 30
  4888.2  2184.1  4894.4  2183.8  4917.7 2181.06  4941.3 2175.29  4946.9 2174.54
    4984 2164.47  4984.3 2163.97  4987.8 2163.97    4988 2164.47  5021.5 2165.57
  5042.3 2167.02  5064.4 2166.72  5070.9 2167.75  5085.3 2167.86    5089 2168.48
  5113.9 2172.21  5134.7 2177.86  5142.5 2179.21  5198.5 2183.46  5241.5 2187.91
  5262.3 2190.79  5270.1 2191.29  5312.4 2197.29  5333.9 2197.92  5348.2 2199.36
  5362.5 2201.95  5376.8 2203.78  5383.4 2203.94  5387.3 2204.86  5390.5 2204.86
#Mann= 6 ,-1 , 0
  4888.2     .07       0  4894.4      .1       0  4917.7     .07       0
    4984     .05       0    4988     .07       0    5089      .1       0
Bank Sta=4984,4988
XS Rating Curve= 0 ,0
Exp/Cntr=0.3,0.1

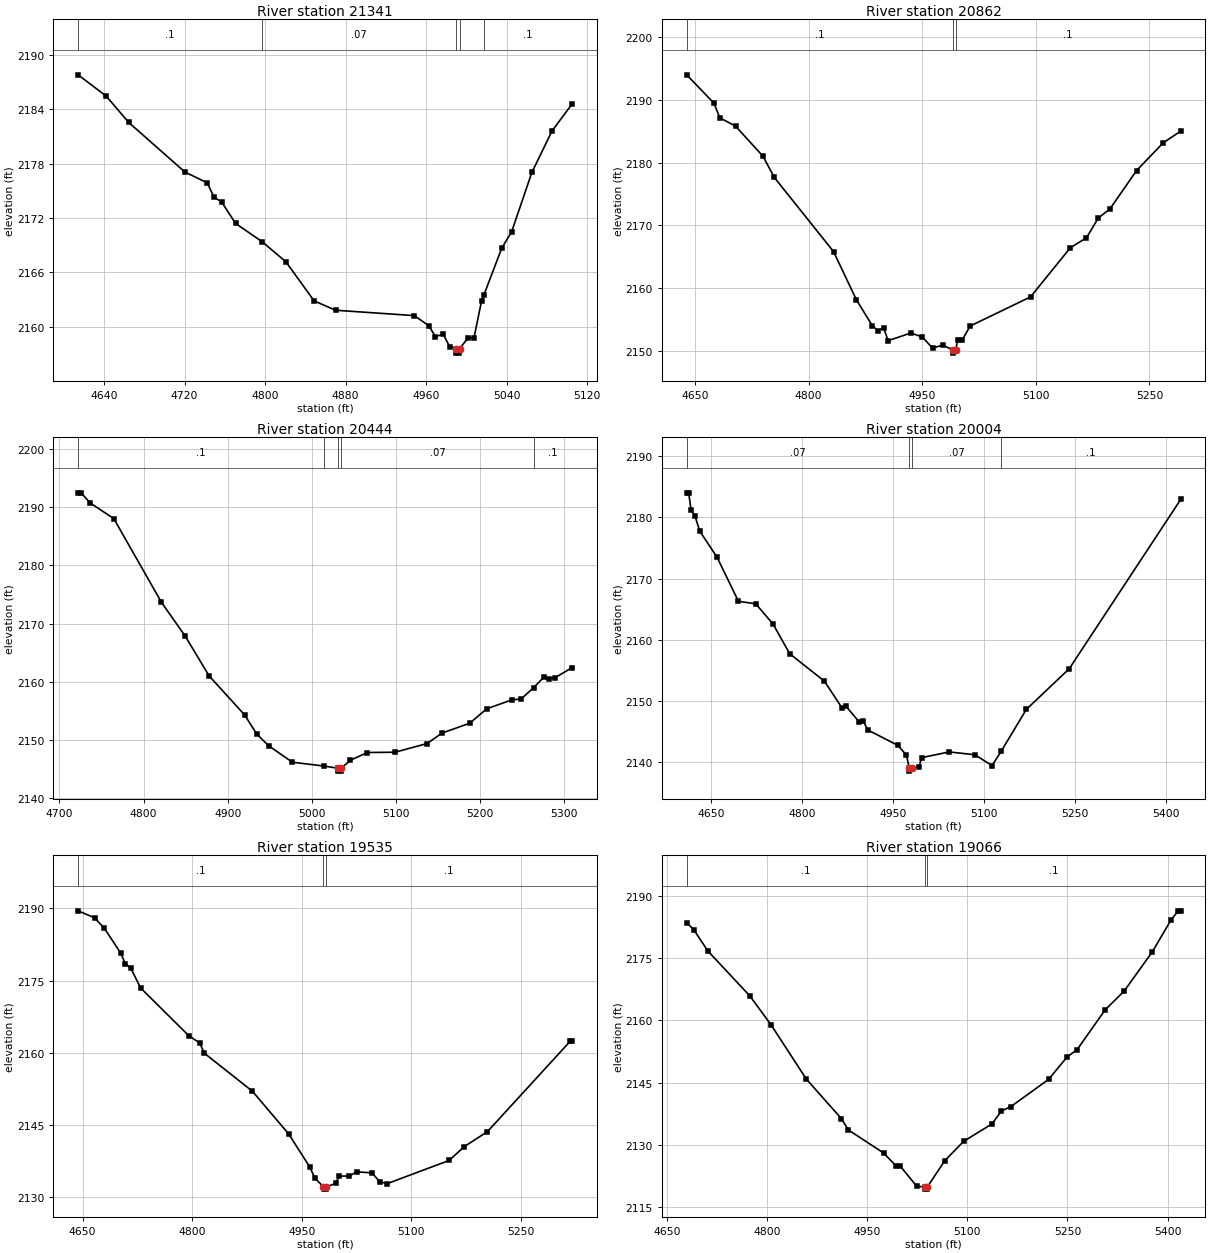
Type RM Length L Ch R = 1 ,21341   ,479,479,479
BEGIN DESCRIPTION:
Frank Baker Creek 47.0
END DESCRIPTION:
XS GIS Cut Line= 3
      1836724.97     13889024.96        1836975.       13889325.
      1837075.04       13889325.
#Sta/Elev= 30
  4614.3 2187.81  4642.3 2185.45  4664.5 2182.56  4720.4 2177.08  4742.6 2175.89
  4749.1 2174.33  4756.9 2173.77  4770.6 2171.42  4797.2 2169.38  4820.7 2167.17
  4848.7 2162.86  4870.1 2161.83  4948.2 2161.24  4962.6 2160.12  4969.1 2158.93
  4976.9 2159.18  4983.4 2157.78  4989.2  2157.6  4989.4  2157.1  4992.9  2157.1
  4993.2  2157.6  5001.6 2158.79  5007.4 2158.79  5014.9 2162.83  5017.1 2163.47
  5034.9 2168.66  5044.9 2170.52  5064.9 2177.04  5084.9 2181.61  5104.9  2184.6
#Mann= 5 ,-1 , 0
  4614.3      .1       0  4797.2     .07       0  4989.2     .05       0
  4993.2     .07       0  5017.1      .1       0
Bank Sta=4989.2,4993.2
XS Rating Curve= 0 ,0
Exp/Cntr=0.3,0.1

Type RM Length L Ch R = 1 ,20862   ,418,418,418
BEGIN DESCRIPTION:
Frank Baker Creek 46.0
END DESCRIPTION:
XS GIS Cut Line= 3
      1836474.98     13889524.98        1836775.       13889725.
      1837024.97     13889874.98
#Sta/Elev= 30
  4639.2 2193.95  4675.3 2189.43  4682.8 2187.13  4703.8 2185.78  4739.9 2181.01
  4754.9 2177.63    4833 2165.86  4863.1 2158.22  4884.1 2154.09  4891.6 2153.27
  4899.1 2153.74  4905.1 2151.68  4935.2 2152.92  4950.2 2152.27  4963.7 2150.52
  4977.2 2150.98  4990.3 2150.21  4990.5 2149.71  4994.3 2150.21  4996.8 2151.76
  5002.7 2151.76  5013.4 2154.02  5093.1 2158.65  5145.6 2166.46  5166.9 2168.04
  5182.5 2171.18    5198 2172.65    5233 2178.73    5268 2183.12  5291.3    2185
#Mann= 3 ,-1 , 0
  4639.2      .1       0  4990.3     .05       0  4994.3      .1       0
Bank Sta=4990.3,4994.3
XS Rating Curve= 0 ,0
Exp/Cntr=0.3,0.1

Type RM Length L Ch R = 1 ,20444   ,440,440,440
BEGIN DESCRIPTION:
Frank Baker Creek 45.0
END DESCRIPTION:
XS GIS Cut Line= 3
      1836274.99     13889774.99        1836475.       13889975.
      1836775.01       13890025.
#Sta/Elev= 30
  4722.2 2192.46  4725.7 2192.46  4736.4 2190.73  4764.6 2188.03  4821.2 2173.65
  4849.5 2167.82  4877.8 2161.01  4920.2 2154.26  4934.3 2151.03  4948.5    2149
  4976.8 2146.16  5014.1 2145.51  5030.9 2145.13  5031.2 2144.63  5034.7 2144.63
  5034.9 2145.13  5045.6 2146.49  5065.9 2147.83  5098.8 2147.88  5136.8 2149.37
  5154.6 2151.17  5187.5 2152.86  5207.8 2155.35  5238.2 2156.91  5248.4    2157
  5263.5 2158.99  5276.2 2160.86  5281.3 2160.49  5288.9 2160.69  5309.2 2162.42
#Mann= 5 ,-1 , 0
  4722.2      .1       0  5014.1     .07       0  5030.9     .05       0
  5034.9     .07       0  5263.5      .1       0
Bank Sta=5030.9,5034.9
XS Rating Curve= 0 ,0
Exp/Cntr=0.3,0.1

Type RM Length L Ch R = 1 ,20004   ,469,469,469
BEGIN DESCRIPTION:
Frank Baker Creek 44.0
END DESCRIPTION:
XS GIS Cut Line= 3
      1835874.99     13890024.99        1836175.       13890275.
      1836475.01     13890575.01
#Sta/Elev= 30
  4609.7 2184.02    4613 2184.02  4616.9 2181.21  4623.4 2180.22  4631.2 2177.77
  4659.8 2173.49    4695 2166.29  4723.6 2165.88  4752.2 2162.56  4779.6 2157.72
  4836.9 2153.23  4865.5 2148.92    4872 2149.19  4894.1 2146.58  4900.6 2146.77
  4908.5 2145.25  4957.9 2142.75  4972.2 2141.14  4976.7 2139.03    4977 2138.53
  4980.7 2139.03  4993.1 2139.27    4997 2140.73  5042.7 2141.67  5085.1  2141.2
  5113.4 2139.43  5128.6 2141.81  5169.9 2148.62  5240.6 2155.26  5424.5 2182.94
#Mann= 4 ,-1 , 0
  4609.7     .07       0  4976.7     .05       0  4980.7     .07       0
  5128.6      .1       0
Bank Sta=4976.7,4980.7
XS Rating Curve= 0 ,0
Exp/Cntr=0.3,0.1

Type RM Length L Ch R = 1 ,19535   ,469,469,469
BEGIN DESCRIPTION:
Frank Baker Creek 43.0
END DESCRIPTION:
XS GIS Cut Line= 3
      1835675.02     13890475.01        1835975.       13890675.
      1836275.04     13890775.01
#Sta/Elev= 30
  4643.8  2189.5  4666.3 2188.05  4679.8 2185.87  4702.4 2180.66  4708.4 2178.52
  4715.9 2177.61  4729.4 2173.48  4795.5 2163.55  4810.5 2162.04  4816.5 2159.95
  4882.6 2152.02  4932.2 2143.16  4960.8 2136.38  4968.3 2133.96  4979.8 2132.19
    4980 2131.69  4983.5 2131.69  4983.8 2132.19  4996.8 2132.86  5001.3 2134.41
  5014.9  2134.4  5025.4 2135.28  5046.5 2135.07    5057 2133.21  5067.6 2132.85
  5151.9 2137.64    5173 2140.53  5204.6 2143.64  5317.9  2162.4  5320.6  2162.4
#Mann= 3 ,-1 , 0
  4643.8      .1       0  4979.8     .05       0  4983.8      .1       0
Bank Sta=4979.8,4983.8
XS Rating Curve= 0 ,0
Exp/Cntr=0.3,0.1

Type RM Length L Ch R = 1 ,19066   ,446,446,446
BEGIN DESCRIPTION:
Frank Baker Creek 42.0
END DESCRIPTION:
XS GIS Cut Line= 3
      1835575.02     13890975.01        1835875.       13891075.
      1836175.02     13891375.02
#Sta/Elev= 30
  4679.2 2183.54  4689.7 2181.91  4710.8 2176.76    4774 2165.88  4805.7 2158.93
  4858.4 2145.89  4911.1 2136.32  4921.6  2133.6  4974.3 2128.04  4992.8 2124.96
  4998.9 2124.96  5023.7 2120.06  5035.8 2119.83  5036.1 2119.33  5039.6 2119.33
  5039.8 2119.83  5066.1  2126.2  5094.4 2130.86  5136.8 2135.05    5151 2138.17
  5165.1 2139.22  5221.7 2145.79    5250  2151.3  5264.1 2152.89  5306.5 2162.56
  5334.8 2167.05  5377.2 2176.55  5405.5 2184.31  5416.1 2186.42  5419.7 2186.42
#Mann= 3 ,-1 , 0
  4679.2      .1       0  5035.8     .05       0  5039.8      .1       0
Bank Sta=5035.8,5039.8
XS Rating Curve= 0 ,0
Exp/Cntr=0.3,0.1

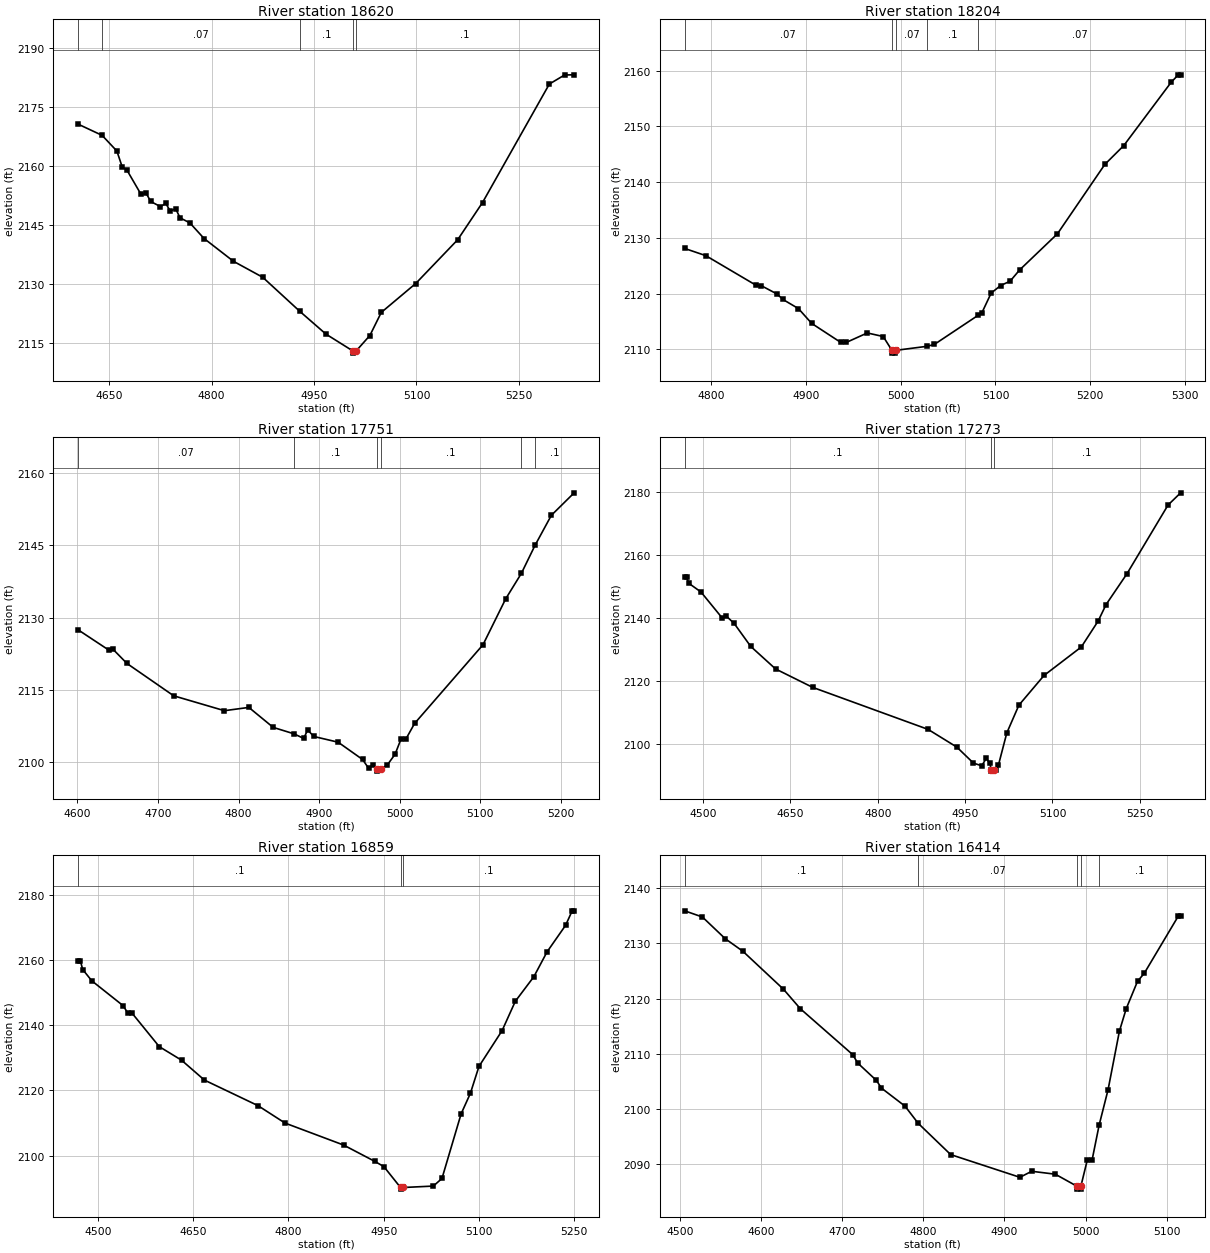
Type RM Length L Ch R = 1 ,18620   ,416,416,416
BEGIN DESCRIPTION:
Frank Baker Creek 41.0
END DESCRIPTION:
XS GIS Cut Line= 3
      1835474.99     13891174.98        1835725.       13891475.
      1836024.96     13891624.98
#Sta/Elev= 30
  4604.9 2170.57  4639.9 2167.73  4661.5 2163.74  4669.4 2159.64  4675.9 2158.99
  4696.7 2152.77  4704.5 2152.98    4711 2150.92  4725.3 2149.62  4733.1 2150.44
  4739.6 2148.47  4747.5 2149.09    4754 2146.76  4768.3 2145.48  4789.1 2141.51
  4832.1 2135.72    4875 2131.65  4929.4 2122.97  4967.4 2117.22  5007.4 2112.87
  5007.7 2112.37  5011.4 2112.87  5031.8 2116.85  5048.5 2122.72  5098.9 2130.07
  5160.3 2141.19  5196.7 2150.66  5294.5 2180.78  5316.9 2183.09  5330.8 2183.12
#Mann= 5 ,-1 , 0
  4604.9      .1       0  4639.9     .07       0  4929.4      .1       0
  5007.4     .05       0  5011.4      .1       0
Bank Sta=5007.4,5011.4
XS Rating Curve= 0 ,0
Exp/Cntr=0.3,0.1

Type RM Length L Ch R = 1 ,18204   ,453,453,453
BEGIN DESCRIPTION:
Frank Baker Creek 40.0
END DESCRIPTION:
XS GIS Cut Line= 3
      1835425.02     13891625.04        1835525.       13891825.
      1835825.04       13891825.
#Sta/Elev= 30
  4771.9  2128.1  4794.2 2126.81  4847.3 2121.49  4852.9 2121.41  4869.7  2119.9
  4875.3 2118.98    4892 2117.31    4906 2114.65  4936.8 2111.23  4942.4 2111.23
  4964.7 2112.94  4981.5  2112.3  4990.7 2109.82  4990.9 2109.32  4994.4 2109.32
  4994.7 2109.82  5027.7 2110.54  5035.5 2110.88    5082 2116.14  5085.5 2116.49
  5095.5  2120.1  5105.5 2121.45  5115.5 2122.23  5125.5 2124.24  5165.5 2130.74
  5215.5 2143.18  5235.5 2146.56  5285.5 2157.91    5293 2159.25  5295.5 2159.25
#Mann= 5 ,-1 , 0
  4771.9     .07       0  4990.7     .05       0  4994.7     .07       0
  5027.7      .1       0    5082     .07       0
Bank Sta=4990.7,4994.7
XS Rating Curve= 0 ,0
Exp/Cntr=0.3,0.1

Type RM Length L Ch R = 1 ,17751   ,478,478,478
BEGIN DESCRIPTION:
Frank Baker Creek 39.0
END DESCRIPTION:
XS GIS Cut Line= 3
      1835174.96     13892174.99        1835575.       13892225.
      1835725.01     13892375.01
#Sta/Elev= 30
  4601.1 2127.47  4638.9  2123.3    4644  2123.5  4661.6 2120.51  4719.6 2113.81
  4782.5 2110.73  4812.8 2111.41    4843 2107.27  4868.6 2105.95  4880.8 2104.99
  4885.8 2106.74  4893.4 2105.39  4923.6  2104.2  4953.9 2100.62  4961.4  2098.8
  4966.5 2099.48  4971.8 2098.71  4972.1 2098.21  4976.2 2098.71  4984.1 2099.38
  4994.2  2101.7  5001.7  2104.9  5007.8  2104.9  5018.4 2108.08  5103.3 2124.39
  5131.5 2133.91  5150.9 2139.17  5167.8 2144.96  5188.1  2151.2  5216.4 2155.86
#Mann= 6 ,-1 , 0
  4601.1     .07       0  4868.6      .1       0  4971.8     .05       0
  4976.2      .1       0  5150.9     .07       0  5167.8      .1       0
Bank Sta=4971.8,4976.2
XS Rating Curve= 0 ,0
Exp/Cntr=0.3,0.1

Type RM Length L Ch R = 1 ,17273   ,414,414,414
BEGIN DESCRIPTION:
Frank Baker Creek 38.0
END DESCRIPTION:
XS GIS Cut Line= 3
      1834975.03     13892275.03        1835375.       13892625.
      1835574.98     13892874.98
#Sta/Elev= 30
  4468.5 2152.99  4471.8 2152.99  4475.6 2151.03  4496.5 2148.26  4532.5 2140.08
  4539.2 2140.71  4553.4 2138.27  4581.9 2130.94  4624.6 2123.75  4688.2  2117.9
  4886.5 2104.51  4935.9 2098.86  4964.4 2093.77  4978.6 2092.92  4986.2 2095.25
  4992.9 2093.65  4994.4 2091.72  4994.7 2091.22  4998.8 2091.72  5003.2 2091.72
  5007.2 2093.09  5021.6 2103.36  5042.4 2112.23  5085.6 2121.69  5149.6 2130.76
  5178.5 2139.02  5192.1 2144.26  5228.1 2154.11  5298.5 2175.95  5320.1 2179.84
#Mann= 3 ,-1 , 0
  4468.5      .1       0  4994.4     .05       0  4998.8      .1       0
Bank Sta=4994.4,4998.8
XS Rating Curve= 0 ,0
Exp/Cntr=0.3,0.1

Type RM Length L Ch R = 1 ,16859   ,445,445,445
BEGIN DESCRIPTION:
Frank Baker Creek 37.0
END DESCRIPTION:
XS GIS Cut Line= 3
      1834724.99     13892474.99        1835075.       13892875.
      1835224.99     13893074.98
#Sta/Elev= 30
  4468.7 2159.76    4472 2159.76  4475.8 2157.06  4490.1  2153.6  4539.4 2145.98
    4547 2143.66  4553.7 2143.64  4596.4 2133.41  4631.5 2129.25  4667.6 2123.14
    4752  2115.3  4794.7 2109.95  4886.8 2103.22  4936.2 2098.19  4950.4 2096.59
  4976.6 2090.19  4976.9 2089.69  4981.1 2090.19  5028.3 2090.63  5041.9 2092.96
  5072.1  2112.8  5086.7 2119.09  5100.2 2127.34  5136.7 2138.34  5157.5 2147.32
  5186.7 2154.86  5207.5 2162.48  5236.7 2170.62  5247.1 2175.07  5250.2 2175.07
#Mann= 3 ,-1 , 0
  4468.7      .1       0  4976.6     .05       0  4981.1      .1       0
Bank Sta=4976.6,4981.1
XS Rating Curve= 0 ,0
Exp/Cntr=0.3,0.1

Type RM Length L Ch R = 1 ,16414   ,446,446,446
BEGIN DESCRIPTION:
Frank Baker Creek 36.0
END DESCRIPTION:
XS GIS Cut Line= 3
      1834324.96     13892824.97        1834725.       13893125.
      1834775.02     13893225.04
#Sta/Elev= 30
  4505.4 2135.88  4527.3 2134.76  4555.4 2130.84  4577.3 2128.55  4627.3 2121.69
  4648.2 2118.15  4712.7 2109.86    4719 2108.32  4741.9  2105.2  4748.2  2103.8
  4777.3 2100.53  4793.5 2097.43  4833.6 2091.77    4919 2087.66  4933.6 2088.75
  4962.7 2088.22  4989.7 2086.02    4990 2085.52  4993.9 2085.52  4994.2 2086.02
  5002.3 2090.88  5008.2 2090.88  5016.8 2097.13  5027.8 2103.52  5041.8 2114.12
  5050.2 2118.18  5064.1 2123.12  5072.5 2124.59  5114.5 2134.94  5117.3 2134.94
#Mann= 5 ,-1 , 0
  4505.4      .1       0  4793.5     .07       0  4989.7     .05       0
  4994.2     .07       0  5016.8      .1       0
Bank Sta=4989.7,4994.2
XS Rating Curve= 0 ,0
Exp/Cntr=0.3,0.1

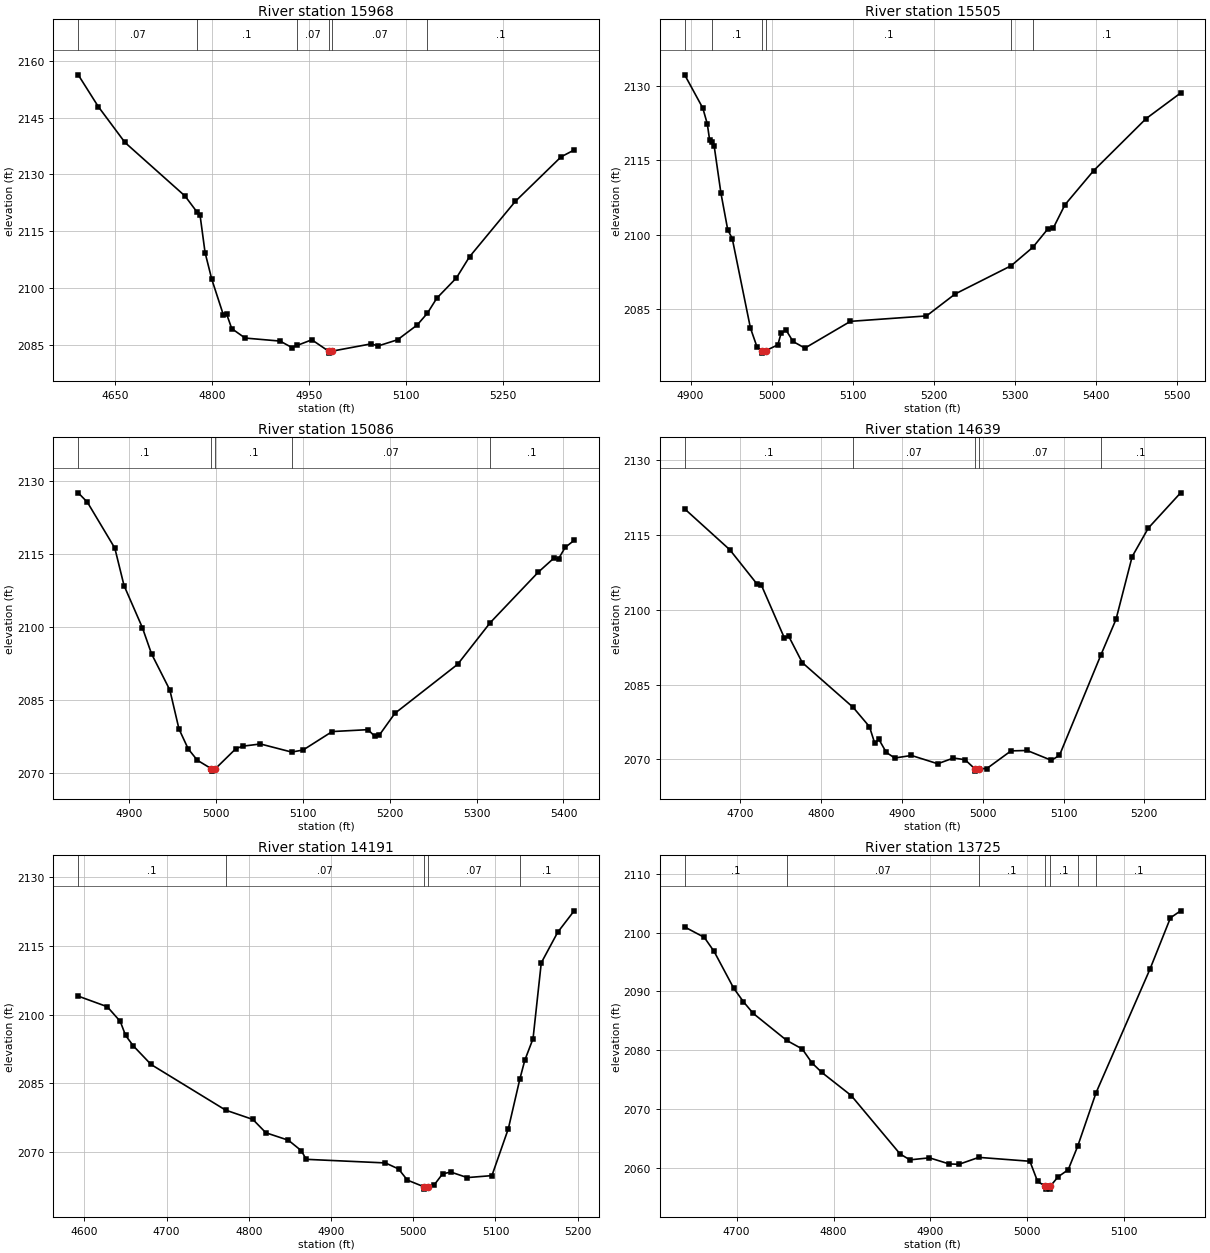
Type RM Length L Ch R = 1 ,15968   ,463,463,463
BEGIN DESCRIPTION:
Frank Baker Creek 35.0
END DESCRIPTION:
XS GIS Cut Line= 3
      1833974.97     13893425.01        1834375.       13893325.
      1834725.01       13893375.
#Sta/Elev= 30
  4593.6 2156.24  4624.6 2147.87  4665.8 2138.43  4758.6 2124.32  4777.5 2120.01
  4781.7 2119.37  4789.5 2109.45  4799.8 2102.44  4817.8 2093.01    4823 2093.15
  4830.7 2089.42  4851.3 2086.93  4905.4 2086.13  4923.5 2084.44  4931.4 2084.97
  4954.4 2086.47  4980.4 2083.46  4980.8 2082.96    4985 2083.46  5046.3 2085.41
  5056.4 2084.83  5086.8 2086.48  5117.1 2090.37  5132.8 2093.46  5147.4 2097.43
  5177.7 2102.77  5197.9 2108.33  5268.6 2122.91  5339.3 2134.64  5359.5 2136.45
#Mann= 6 ,-1 , 0
  4593.6     .07       0  4777.5      .1       0  4931.4     .07       0
  4980.4     .05       0    4985     .07       0  5132.8      .1       0
Bank Sta=4980.4,4985
XS Rating Curve= 0 ,0
Exp/Cntr=0.3,0.1

Type RM Length L Ch R = 1 ,15505   ,419,419,419
BEGIN DESCRIPTION:
Frank Baker Creek 34.0
END DESCRIPTION:
XS GIS Cut Line= 3
        1834175.       13893775.        1834275.       13893725.
        1834675.       13893425.
#Sta/Elev= 30
  4892.8 2132.15  4915.2 2125.45  4920.7 2122.28  4923.5 2119.12    4926 2118.59
  4929.1 2117.93  4937.5 2108.38  4945.9    2101  4951.5 2099.22  4973.9 2081.25
  4982.2 2077.35  4988.3 2076.69  4988.6 2076.19    4993 2076.69  5007.7 2077.86
  5011.9 2080.26  5018.1 2080.76  5026.5 2078.53  5041.1  2077.2  5097.3 2082.58
  5191.1 2083.67  5226.5 2088.09  5295.5 2093.76  5322.3 2097.47  5341.1 2101.22
  5347.3 2101.27  5361.9 2106.02  5397.3 2112.88  5461.9 2123.33  5504.6 2128.49
#Mann= 6 ,-1 , 0
  4892.8     .07       0    4926      .1       0  4988.3     .05       0
    4993      .1       0  5295.5     .07       0  5322.3      .1       0
Bank Sta=4988.3,4993
XS Rating Curve= 0 ,0
Exp/Cntr=0.3,0.1

Type RM Length L Ch R = 1 ,15086   ,447,447,447
BEGIN DESCRIPTION:
Frank Baker Creek 33.0
END DESCRIPTION:
XS GIS Cut Line= 3
      1834325.03     13894124.99        1834475.       13894075.
        1834875.       13893975.
#Sta/Elev= 30
  4841.9 2127.55  4852.4 2125.63    4884 2116.19  4894.6  2108.5  4915.7 2099.85
  4926.2 2094.48  4947.3 2087.03  4957.8 2079.03  4968.4 2074.94  4978.9 2072.61
    4995 2070.87  4995.4 2070.37  4999.7 2070.87  5023.2 2074.98  5030.9 2075.49
  5051.5 2075.95  5087.3 2074.29  5100.5  2074.7    5134  2078.5  5175.2 2078.89
  5182.9 2077.54  5188.1 2077.74  5206.1 2082.24  5278.3 2092.32  5315.8 2100.88
  5371.1 2111.26  5389.1 2114.15  5394.3 2113.99    5402 2116.34  5412.3 2117.78
#Mann= 5 ,-1 , 0
  4841.9      .1       0    4995     .05       0  4999.7      .1       0
  5087.3     .07       0  5315.8      .1       0
Bank Sta=4995,4999.7
XS Rating Curve= 0 ,0
Exp/Cntr=0.3,0.1

Type RM Length L Ch R = 1 ,14639   ,448,448,448
BEGIN DESCRIPTION:
Frank Baker Creek 32.0
END DESCRIPTION:
XS GIS Cut Line= 3
      1834374.98     13894324.99        1834725.       13894425.
      1834974.97       13894425.
#Sta/Elev= 30
  4630.9 2120.23  4686.8 2112.03  4720.6 2105.13  4725.8 2104.96  4754.4 2094.32
  4759.6 2094.72  4776.5  2089.4  4839.5 2080.42  4859.7 2076.55  4866.2 2073.22
  4871.4 2073.99  4880.5  2071.4  4890.9 2070.27  4911.7 2070.78  4944.2 2069.12
  4963.7 2070.27    4978 2069.93  4989.9 2068.14  4990.3 2067.64  4994.7 2068.14
  5004.9 2068.15  5034.9  2071.7  5054.9 2071.78  5084.9 2069.81  5094.9  2070.8
    5146 2090.86  5164.9 2098.07  5184.9 2110.66  5204.9 2116.38  5244.9 2123.45
#Mann= 5 ,-1 , 0
  4630.9      .1       0  4839.5     .07       0  4989.9     .05       0
  4994.7     .07       0    5146      .1       0
Bank Sta=4989.9,4994.7
XS Rating Curve= 0 ,0
Exp/Cntr=0.3,0.1

Type RM Length L Ch R = 1 ,14191   ,466,466,466
BEGIN DESCRIPTION:
Frank Baker Creek 31.0
END DESCRIPTION:
XS GIS Cut Line= 3
      1834424.98     13895025.01        1834775.       13894825.
      1834974.96       13894825.
#Sta/Elev= 30
  4592.6 2104.07  4627.9 2101.76  4643.7 2098.56  4650.2 2095.49  4659.6 2093.21
  4681.2 2089.14  4771.8 2079.18    4805 2077.14  4820.8 2074.23  4848.2  2072.6
    4864  2070.3  4869.8 2068.43  4966.2 2067.64  4982.1 2066.33  4992.9 2063.89
  5013.2 2062.42  5013.5 2061.92  5018.3 2062.42  5025.7 2062.89  5035.7 2065.25
  5045.7 2065.65  5065.7 2064.44  5095.7 2064.87  5115.7 2075.14  5129.6 2085.92
  5135.7 2090.07  5145.7 2094.78  5155.7 2111.34  5175.7 2118.02  5195.7  2122.7
#Mann= 5 ,-1 , 0
  4592.6      .1       0  4771.8     .07       0  5013.2     .05       0
  5018.3     .07       0  5129.6      .1       0
Bank Sta=5013.2,5018.3
XS Rating Curve= 0 ,0
Exp/Cntr=0.3,0.1

Type RM Length L Ch R = 1 ,13725   ,468,468,468
BEGIN DESCRIPTION:
Frank Baker Creek 30.0
END DESCRIPTION:
XS GIS Cut Line= 3
      1834474.97       13895225.        1834825.       13895275.
        1834975.       13895225.
#Sta/Elev= 30
  4646.4 2100.94  4666.6 2099.18  4676.7  2096.8  4696.9 2090.57    4707 2088.25
  4717.1 2086.27  4751.7 2081.68  4767.7 2080.23  4777.8 2077.85  4787.9 2076.25
  4818.2 2072.33  4868.7  2062.4  4878.8 2061.41    4899 2061.75  4919.2 2060.72
  4929.3 2060.65  4949.9 2061.83  5002.6 2061.17  5010.5 2057.75  5018.5 2056.94
  5018.9 2056.44  5023.3 2056.44  5023.7 2056.94  5031.6 2058.52  5042.1 2059.73
  5051.9 2063.72  5070.8 2072.78  5126.5 2093.79  5147.6 2102.49  5158.1 2103.68
#Mann= 7 ,-1 , 0
  4646.4      .1       0  4751.7     .07       0  4949.9      .1       0
  5018.5     .05       0  5023.7      .1       0  5051.9     .07       0
  5070.8      .1       0
Bank Sta=5018.5,5023.7
XS Rating Curve= 0 ,0
Exp/Cntr=0.3,0.1

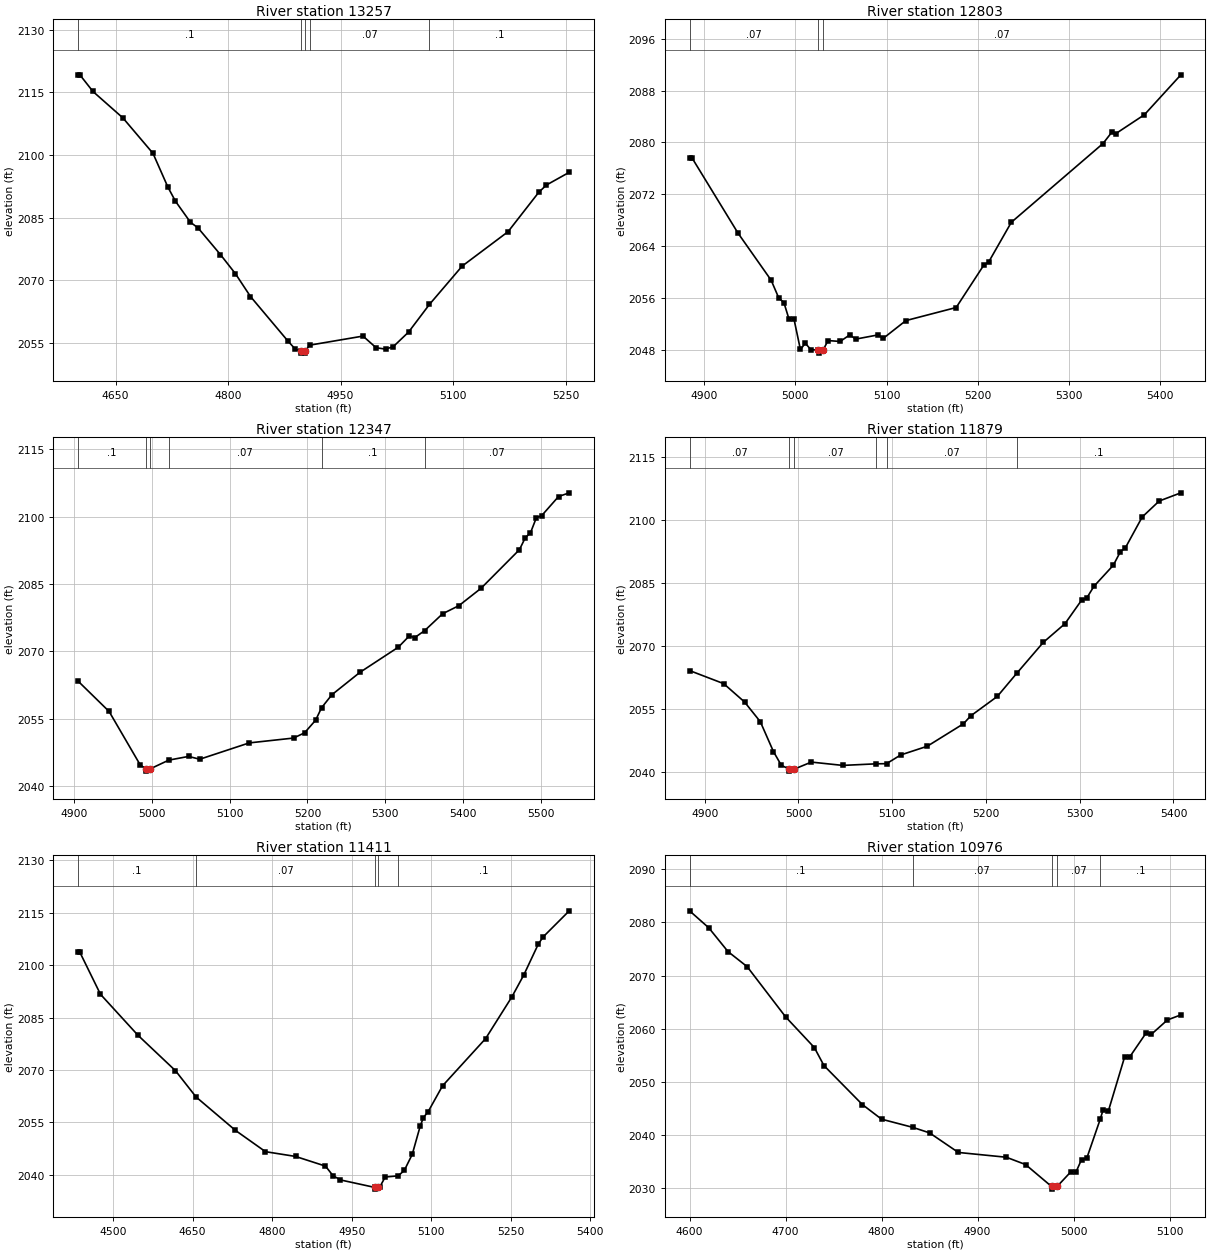
Type RM Length L Ch R = 1 ,13257   ,454,454,454
BEGIN DESCRIPTION:
Frank Baker Creek 29.0
END DESCRIPTION:
XS GIS Cut Line= 3
      1834374.95       13895725.        1834775.       13895725.
        1835025.       13895775.
#Sta/Elev= 30
  4599.9 2119.24  4602.4 2119.24  4619.9 2115.24  4659.9 2108.88  4699.9  2100.4
  4719.9 2092.25  4729.9  2088.9  4749.9 2083.85  4759.9 2082.52  4789.9 2076.09
  4809.9  2071.5  4829.9 2066.04  4879.9 2055.34  4889.9 2053.37  4897.3 2052.96
  4897.7 2052.46  4902.2 2052.46  4902.6 2052.96  4909.1 2054.38  4979.9 2056.55
  4997.4 2053.75  5010.1 2053.42  5020.3 2054.02  5040.7 2057.52  5068.4 2064.13
  5112.1 2073.34  5173.3  2081.6  5214.1 2091.02  5224.3 2092.78  5254.9 2095.85
#Mann= 5 ,-1 , 0
  4599.9      .1       0  4897.3     .05       0  4902.6      .1       0
  4909.1     .07       0  5068.4      .1       0
Bank Sta=4897.3,4902.6
XS Rating Curve= 0 ,0
Exp/Cntr=0.3,0.1

Type RM Length L Ch R = 1 ,12803   ,456,456,456
BEGIN DESCRIPTION:
Frank Baker Creek 28.0
END DESCRIPTION:
XS GIS Cut Line= 3
      1834524.97     13896074.98        1834625.       13896125.
      1835024.96     13895975.01
#Sta/Elev= 30
  4883.9 2077.59  4886.7 2077.59    4937 2066.02  4973.4 2058.74  4981.8 2055.99
  4987.4 2055.29  4992.9 2052.78  4998.4 2052.78  5005.5 2048.05  5010.9 2049.01
  5017.1 2048.01  5025.1 2047.99  5025.5 2047.49  5030.5 2047.99  5035.8 2049.43
  5049.1 2049.29  5059.8 2050.32    5066 2049.65    5091 2050.31  5096.3 2049.76
  5121.2 2052.51  5176.4 2054.53  5206.7 2061.07    5212 2061.54  5236.9 2067.68
  5337.5 2079.84  5347.3 2081.61  5351.7 2081.38  5382.9 2084.28  5422.9 2090.44
#Mann= 3 ,-1 , 0
  4883.9     .07       0  5025.1     .05       0  5030.5     .07       0
Bank Sta=5025.1,5030.5
XS Rating Curve= 0 ,0
Exp/Cntr=0.3,0.1

Type RM Length L Ch R = 1 ,12347   ,468,468,468
BEGIN DESCRIPTION:
Frank Baker Creek 27.0
END DESCRIPTION:
XS GIS Cut Line= 3
      1834624.95       13896525.        1834725.       13896525.
      1835125.03     13896174.97
#Sta/Elev= 30
    4905 2063.38    4945  2056.6    4985 2044.69  4992.3  2043.8  4992.7  2043.3
  4997.8  2043.8  5021.7 2045.75  5047.3 2046.58  5061.5 2045.95  5125.1 2049.59
  5182.1 2050.67  5196.3 2051.84  5210.5 2054.65  5218.2 2057.44  5231.4 2060.32
  5267.5 2065.32  5316.8 2070.92  5331.1 2073.46  5337.7 2073.03  5350.7 2074.62
  5373.8 2078.38  5394.7 2080.18  5423.1 2084.04  5472.5 2092.65  5480.1 2095.33
  5486.7  2096.4  5494.3 2099.78    5501 2100.22  5522.8  2104.5  5536.6 2105.33
#Mann= 6 ,-1 , 0
    4905      .1       0  4992.3     .05       0  4997.8      .1       0
  5021.7     .07       0  5218.2      .1       0  5350.7     .07       0
Bank Sta=4992.3,4997.8
XS Rating Curve= 0 ,0
Exp/Cntr=0.3,0.1

Type RM Length L Ch R = 1 ,11879   ,468,468,468
BEGIN DESCRIPTION:
Frank Baker Creek 26.0
END DESCRIPTION:
XS GIS Cut Line= 3
      1834824.97     13896975.01        1834925.       13896925.
      1835324.96     13896825.01
#Sta/Elev= 30
  4883.8 2064.17  4920.2 2061.06  4942.5 2056.69  4959.3    2052  4973.3  2044.9
  4981.7 2041.64    4990 2040.76  4990.4 2040.26  4995.7 2040.76  5013.7 2042.41
  5047.2 2041.62  5083.1    2042  5093.9 2042.03    5109  2044.1  5137.4 2046.18
    5176 2051.52  5183.7 2053.39  5212.1 2058.02  5233.1 2063.59  5261.1 2070.86
  5284.3 2075.32  5302.3    2081  5307.4 2081.38  5315.2 2084.21  5335.8  2089.2
  5343.5 2092.46  5348.7 2093.35  5366.7 2100.69  5384.8 2104.48  5407.9 2106.43
#Mann= 6 ,-1 , 0
  4883.8     .07       0    4990     .05       0  4995.7     .07       0
  5083.1      .1       0  5093.9     .07       0  5233.1      .1       0
Bank Sta=4990,4995.7
XS Rating Curve= 0 ,0
Exp/Cntr=0.3,0.1

Type RM Length L Ch R = 1 ,11411   ,435,435,435
BEGIN DESCRIPTION:
Frank Baker Creek 25.0
END DESCRIPTION:
XS GIS Cut Line= 3
      1834825.03     13897674.97        1835225.       13897275.
        1835525.       13897075.
#Sta/Elev= 30
  4434.1  2103.7  4437.6  2103.7  4476.5 2091.66  4547.2 2079.93  4617.9 2069.79
  4656.7 2062.27    4731  2052.7  4787.6 2046.61  4844.2 2045.25  4900.7 2042.48
  4914.9 2039.74    4929 2038.52  4993.3 2036.39  4993.8 2035.89  4999.1 2036.39
  5002.7 2036.39  5013.3 2039.36  5037.7 2039.68  5049.3 2041.24  5064.3 2045.85
  5079.4 2053.99  5085.4 2056.38  5094.4  2058.1  5121.4 2065.46  5202.6 2078.98
  5252.1 2090.91  5274.7 2097.23  5301.7 2105.95  5310.7 2108.03  5360.3 2115.55
#Mann= 5 ,-1 , 0
  4434.1      .1       0  4656.7     .07       0  4993.3     .05       0
  4999.1     .07       0  5037.7      .1       0
Bank Sta=4993.3,4999.1
XS Rating Curve= 0 ,0
Exp/Cntr=0.3,0.1

Type RM Length L Ch R = 1 ,10976   ,486,486,486
BEGIN DESCRIPTION:
Frank Baker Creek 24.0
END DESCRIPTION:
XS GIS Cut Line= 3
      1834925.04       13897675.        1835325.       13897675.
      1835425.03     13897725.02
#Sta/Elev= 30
    4600 2082.15    4620 2078.96    4640  2074.5    4660 2071.66    4700 2062.24
    4730 2056.46    4740 2053.08    4780 2045.76    4800 2043.01  4832.4 2041.48
    4850 2040.44    4880 2036.76    4930 2035.86    4950 2034.49  4977.1 2030.37
  4977.5 2029.87  4982.9 2030.37  4997.5 2033.18  5002.8 2033.18  5008.3 2035.41
  5013.9 2035.73  5027.7 2042.95  5030.7 2044.69  5036.3 2044.55  5053.1 2054.63
  5058.7 2054.75  5075.4 2059.15    5081 2058.94  5097.8 2061.65  5111.8  2062.6
#Mann= 5 ,-1 , 0
    4600      .1       0  4832.4     .07       0  4977.1     .05       0
  4982.9     .07       0  5027.7      .1       0
Bank Sta=4977.1,4982.9
XS Rating Curve= 0 ,0
Exp/Cntr=0.3,0.1