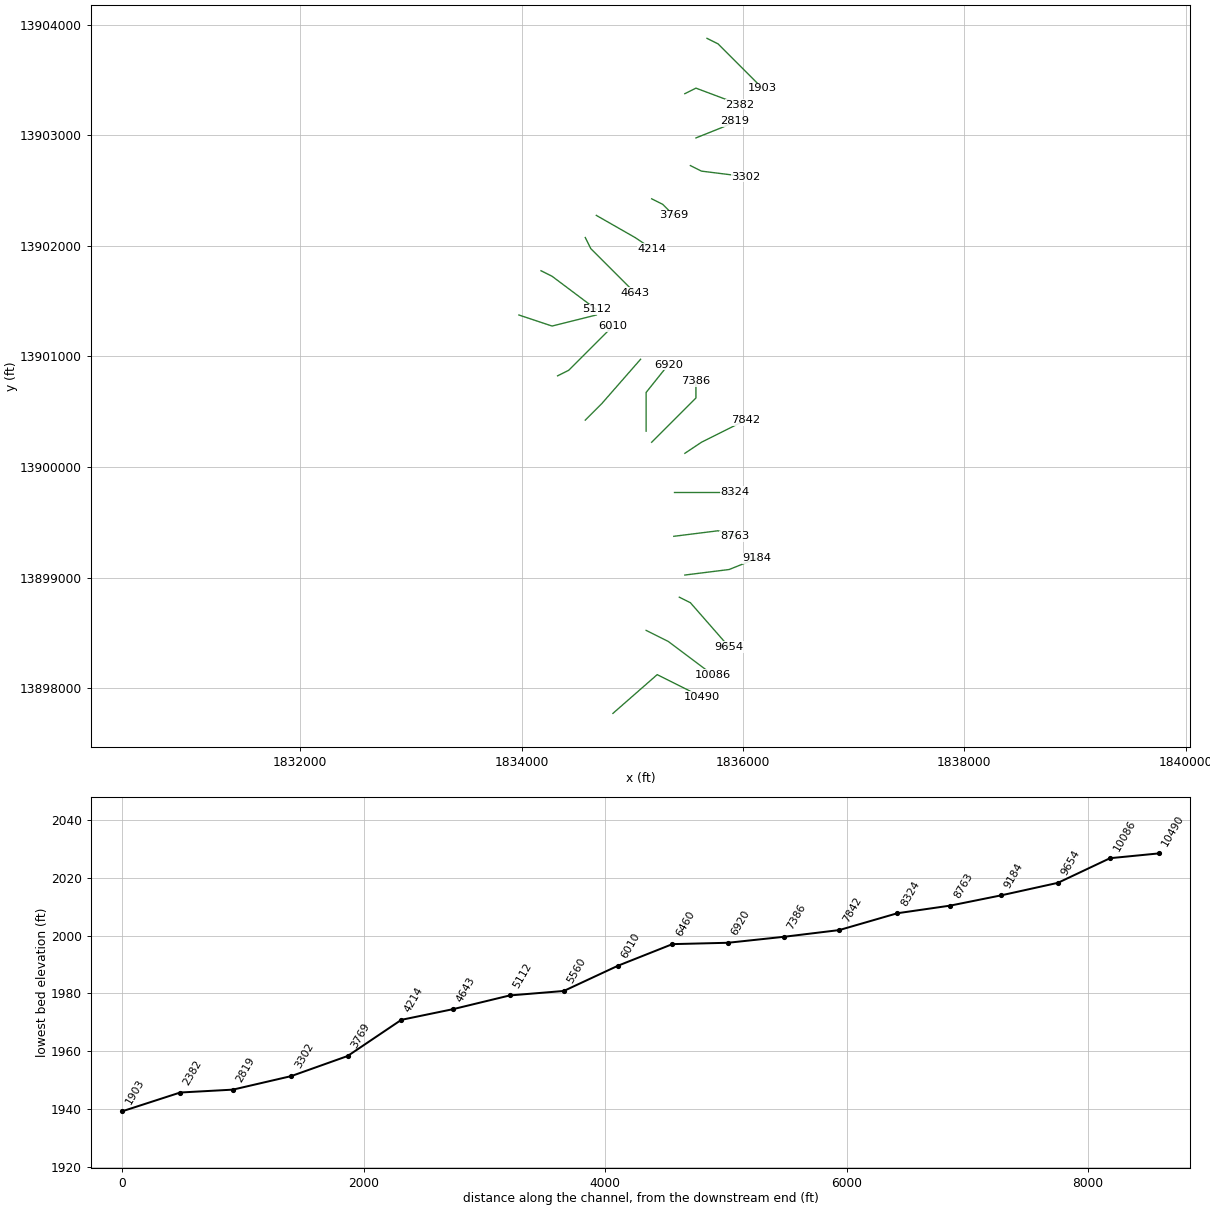
HEC-RAS study Frank Baker Creek.prj: Frank Baker Creek Base Level Engineering

--- Frank Baker Creek.g01 (geometry) --- (continued)

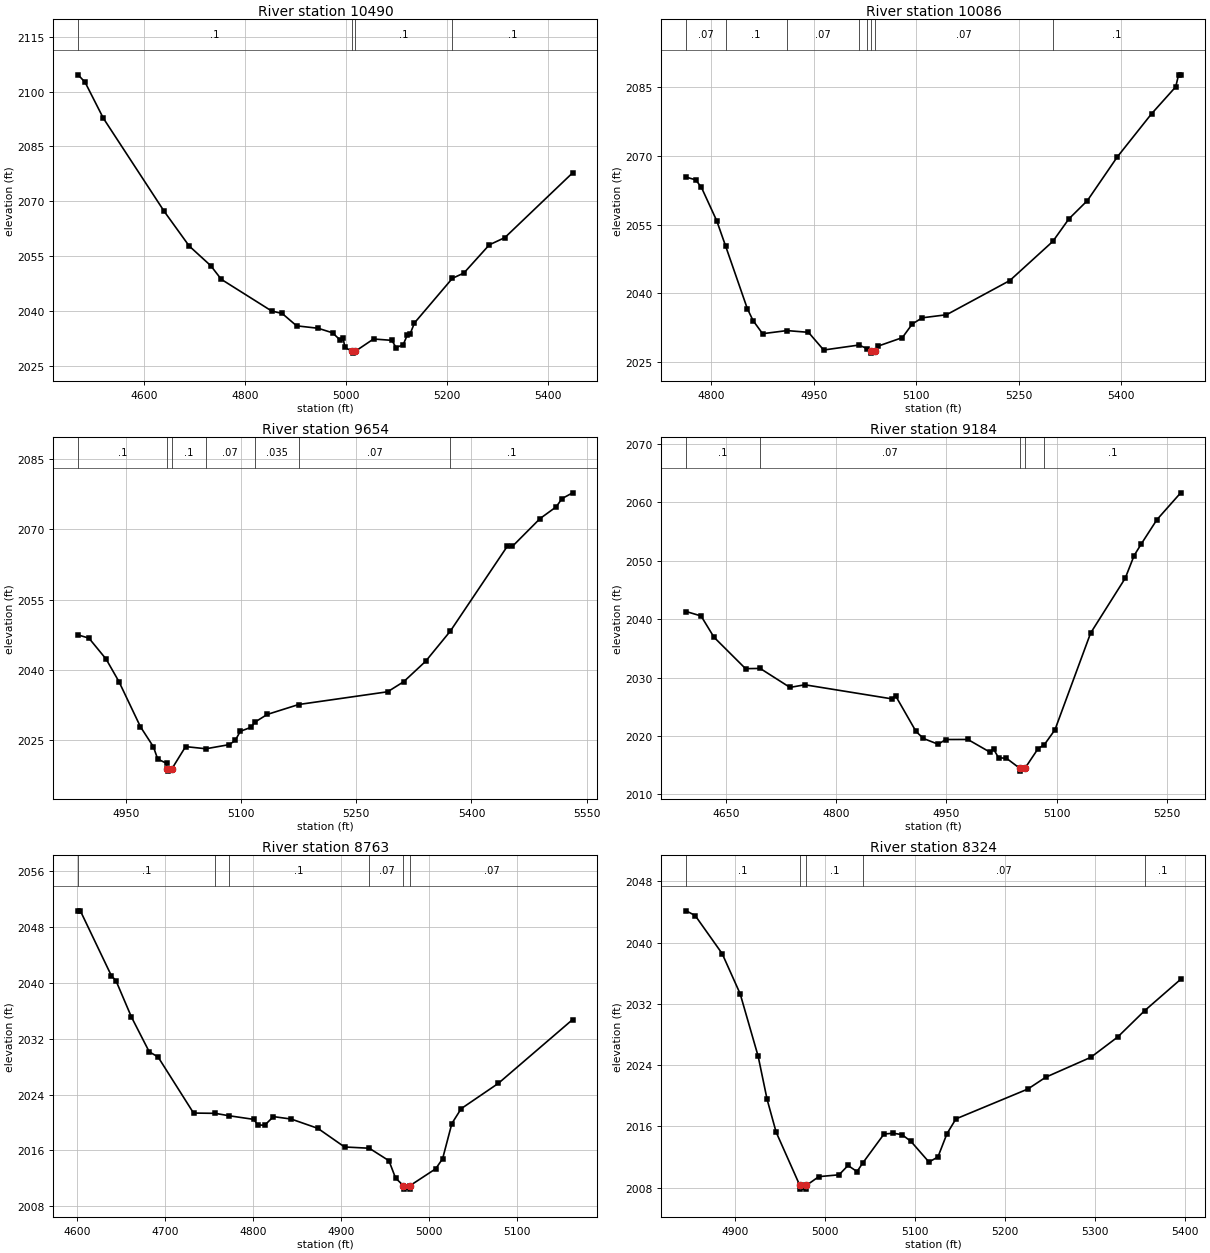
Type RM Length L Ch R = 1 ,10490   ,404,404,404
BEGIN DESCRIPTION:
Frank Baker Creek 23.0
END DESCRIPTION:
XS GIS Cut Line= 3
      1834824.97     13897774.97        1835225.       13898125.
      1835625.03     13897924.98
#Sta/Elev= 30
  4469.8 2104.58  4483.6 2102.53  4519.7 2092.72  4640.2 2067.26  4689.6 2057.81
  4732.3 2052.43  4753.2  2048.7  4852.8 2040.05  4873.7 2039.37  4902.2    2036
  4944.9 2035.33  4973.4 2034.09  4987.6 2032.22  4994.2 2032.61    4998 2030.08
  5012.4 2029.04  5012.9 2028.54  5018.3 2029.04  5054.5  2032.4  5090.8 2032.03
  5099.2 2030.04  5113.2 2030.84  5121.5 2033.54  5127.1 2033.85  5135.5 2036.79
  5210.6 2048.98  5233.3 2050.42  5283.7 2058.13  5314.4  2060.1  5448.6  2077.8
#Mann= 4 ,-1 , 0
  4469.8      .1       0  5012.4     .05       0  5018.3      .1       0
  5210.6      .1       0
Bank Sta=5012.4,5018.3
XS Rating Curve= 0 ,0
Exp/Cntr=0.3,0.1

Type RM Length L Ch R = 1 ,10086   ,432,432,432
BEGIN DESCRIPTION:
Frank Baker Creek 22.0
END DESCRIPTION:
XS GIS Cut Line= 3
      1835125.03     13898524.99        1835325.       13898425.
      1835725.02     13898124.99
#Sta/Elev= 30
  4763.4 2065.37  4777.3 2064.78  4785.7 2063.12  4808.1 2055.82    4821 2050.33
  4852.8 2036.63  4861.2 2034.01  4875.2 2031.13  4910.8 2031.81  4942.3 2031.43
  4964.6 2027.56  5016.2 2028.65  5028.3 2027.85    5034 2027.38  5034.5 2026.88
  5039.9 2027.38  5044.3 2028.42  5079.7 2030.27  5094.3 2033.27  5108.9 2034.61
  5144.3 2035.27    5237 2042.76  5299.9 2051.32  5323.4 2056.24  5350.5 2060.25
  5394.3 2069.81  5444.3 2079.22  5479.7 2085.12  5483.9 2087.75    5487 2087.75
#Mann= 8 ,-1 , 0
  4763.4     .07       0    4821      .1       0  4910.8     .07       0
  5016.2    .035       0  5028.3     .07       0    5034     .05       0
  5039.9     .07       0  5299.9      .1       0
Bank Sta=5034,5039.9
XS Rating Curve= 0 ,0
Exp/Cntr=0.3,0.1

Type RM Length L Ch R = 1 ,9654    ,470,470,470
BEGIN DESCRIPTION:
Frank Baker Creek 21.0
END DESCRIPTION:
XS GIS Cut Line= 3
      1835424.96     13898825.02        1835525.       13898775.
      1835875.03     13898374.96
#Sta/Elev= 30
  4888.2 2047.44  4902.2 2046.77  4924.6 2042.28  4941.3 2037.47  4969.3 2027.81
  4986.1 2023.55  4991.7 2020.93  5003.4 2019.99  5004.2 2018.84  5004.7 2018.34
  5010.2 2018.84    5028 2023.58  5054.5 2023.12    5085 2024.01  5092.6 2024.92
  5099.2 2026.84  5113.5 2027.74  5117.7 2028.76  5134.3 2030.46  5175.2 2032.58
  5290.9  2035.3  5311.8 2037.45  5340.3 2041.81  5372.5 2048.27  5446.6  2066.4
  5453.2 2066.37  5489.3 2072.33  5510.2 2074.82  5517.8 2076.59  5531.6 2077.82
#Mann= 7 ,-1 , 0
  4888.2      .1       0  5004.2     .05       0  5010.2      .1       0
  5054.5     .07       0  5117.7    .035       0  5175.2     .07       0
  5372.5      .1       0
Bank Sta=5004.2,5010.2
XS Rating Curve= 0 ,0
Exp/Cntr=0.3,0.1

Type RM Length L Ch R = 1 ,9184    ,421,421,421
BEGIN DESCRIPTION:
Frank Baker Creek 20.0
END DESCRIPTION:
XS GIS Cut Line= 3
      1835474.96       13899025.        1835875.       13899075.
      1836124.99       13899175.
#Sta/Elev= 30
  4596.1 2041.32  4616.3 2040.56  4633.9 2036.92  4676.8 2031.54  4696.7 2031.58
  4737.2 2028.33  4757.4 2028.78  4875.8 2026.37  4880.8  2026.9  4908.5 2020.81
  4918.6 2019.59  4938.8  2018.6  4948.9 2019.41  4979.1 2019.42  5008.7 2017.28
  5014.1 2017.77  5020.8 2016.29  5031.6  2016.2  5049.5  2014.5    5050    2014
  5056.8  2014.5  5074.6 2017.85  5083.1 2018.53  5097.5 2021.07    5146 2037.63
  5193.1 2047.03  5205.2 2050.91  5214.7 2052.85  5236.2 2057.05  5268.5 2061.64
#Mann= 5 ,-1 , 0
  4596.1      .1       0  4696.7     .07       0  5049.5     .05       0
  5056.8     .07       0  5083.1      .1       0
Bank Sta=5049.5,5056.8
XS Rating Curve= 0 ,0
Exp/Cntr=0.3,0.1

Type RM Length L Ch R = 1 ,8763    ,439,439,439
BEGIN DESCRIPTION:
Frank Baker Creek 19.0
END DESCRIPTION:
XS GIS Cut Line= 3
      1835374.97       13899375.        1835775.       13899425.
      1835925.04     13899374.99
#Sta/Elev= 30
  4601.4 2050.33  4603.9 2050.33  4639.2 2041.01  4644.3 2040.33  4661.9 2035.11
  4682.1 2030.13  4692.1 2029.39  4732.4 2021.35    4757 2021.31  4772.4 2020.97
  4800.5 2020.45  4805.5 2019.65  4813.1  2019.6  4823.1 2020.84  4843.3 2020.49
  4873.5 2019.16  4903.8 2016.49  4931.9 2016.31  4954.2 2014.52  4961.7 2012.04
  4970.6 2010.95  4971.1 2010.45  4977.6 2010.45  4978.1 2010.95  5007.2 2013.36
  5015.1  2014.8  5025.6 2019.85  5036.2 2021.98  5078.3  2025.6  5162.7 2034.75
#Mann= 6 ,-1 , 0
  4601.4      .1       0    4757     .07       0  4772.4      .1       0
  4931.9     .07       0  4970.6     .05       0  4978.1     .07       0
Bank Sta=4970.6,4978.1
XS Rating Curve= 0 ,0
Exp/Cntr=0.3,0.1

Type RM Length L Ch R = 1 ,8324    ,482,482,482
BEGIN DESCRIPTION:
Frank Baker Creek 18.0
END DESCRIPTION:
XS GIS Cut Line= 3
      1835374.96       13899775.        1835525.       13899775.
      1835924.96       13899775.
#Sta/Elev= 30
  4845.7 2044.14  4855.7 2043.52  4885.7 2038.55  4905.7 2033.31  4925.7 2025.16
  4935.7 2019.51  4945.7 2015.25    4972  2008.3  4972.5  2007.8    4979  2007.8
  4979.5  2008.3  4993.2 2009.43  5015.7 2009.67  5025.7 2010.89  5035.7 2010.09
    5042  2011.2  5065.7 2014.99  5075.7  2015.1  5085.7 2014.92  5095.7 2014.03
  5115.7 2011.34  5125.7    2012  5135.7 2015.03  5145.7 2016.97  5225.7 2020.87
  5245.7 2022.42  5295.7 2025.01  5325.7 2027.67  5355.5 2031.09  5395.7  2035.2
#Mann= 5 ,-1 , 0
  4845.7      .1       0    4972     .05       0  4979.5      .1       0
    5042     .07       0  5355.5      .1       0
Bank Sta=4972,4979.5
XS Rating Curve= 0 ,0
Exp/Cntr=0.3,0.1

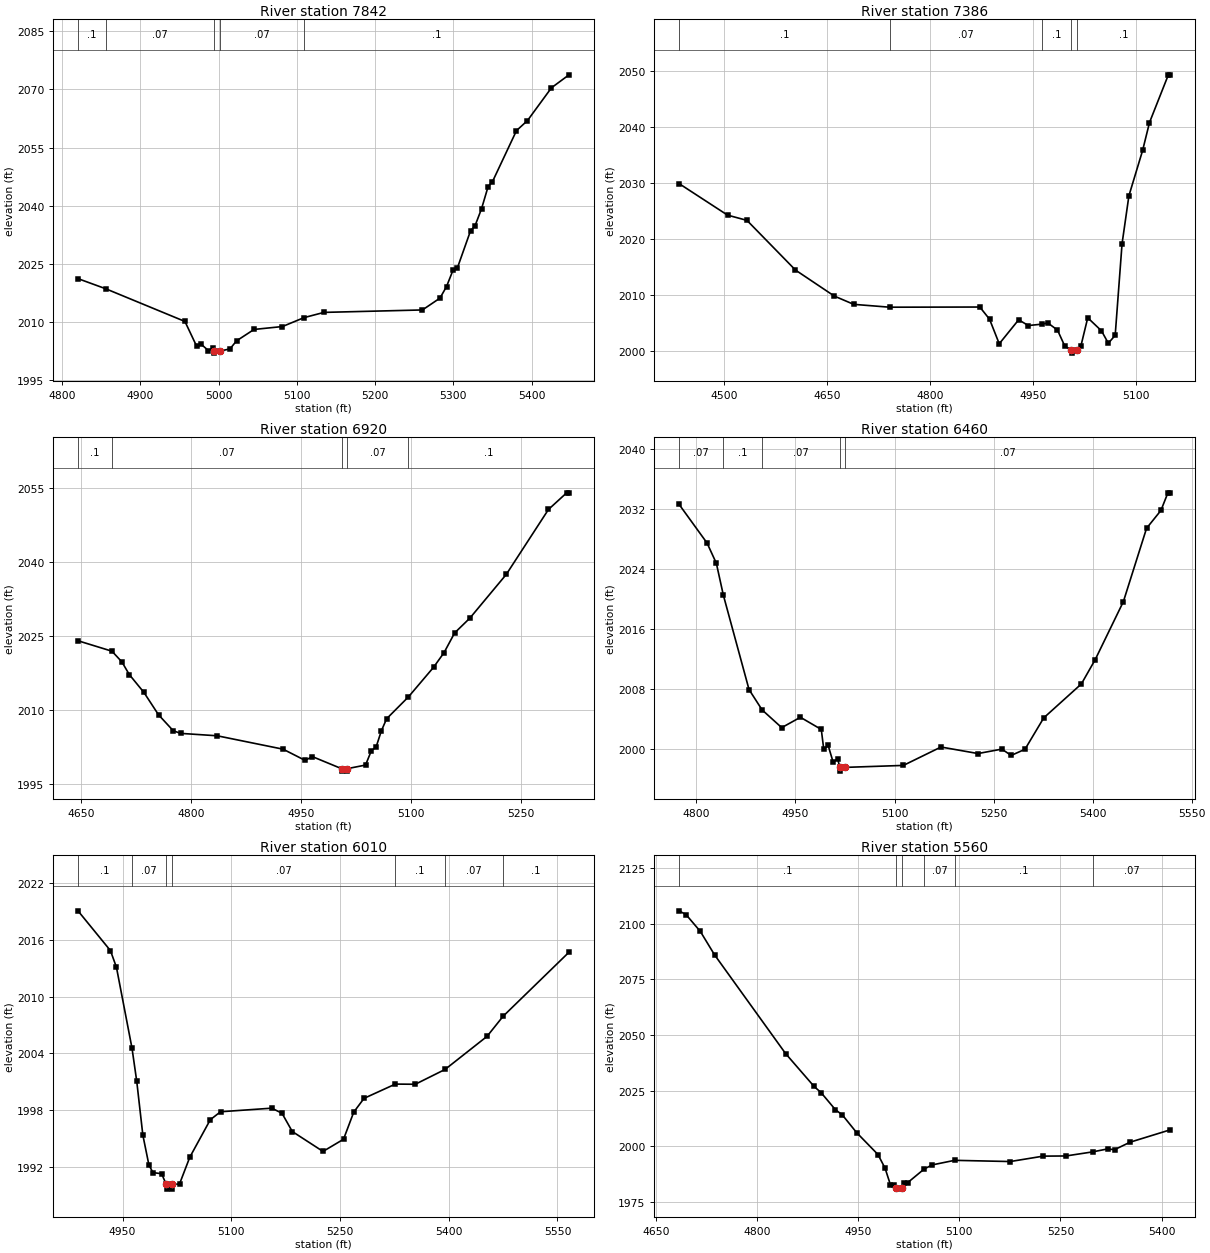
Type RM Length L Ch R = 1 ,7842    ,456,456,456
BEGIN DESCRIPTION:
Frank Baker Creek 17.0
END DESCRIPTION:
XS GIS Cut Line= 3
        1835475.       13900125.        1835625.       13900225.
      1836025.01       13900425.
#Sta/Elev= 30
  4820.2 2021.18  4855.5 2018.58  4956.9 2010.13  4971.9 2003.72  4977.9  2004.2
    4987  2002.6    4993  2003.4  4993.7 2002.46  4994.2 2001.96  5001.2 2002.46
  5014.5 2003.06  5022.8 2005.12  5045.2 2008.07  5081.5 2008.82  5109.1 2011.12
  5134.6 2012.47  5260.4  2013.1  5282.8 2016.15  5291.2 2019.14  5299.6 2023.43
  5305.1 2023.96  5321.9 2033.54  5327.5 2034.75  5335.9 2039.19  5344.3 2044.91
  5349.9  2046.2  5380.6 2059.37  5394.6 2061.95  5425.3 2070.42  5447.7 2073.76
#Mann= 5 ,-1 , 0
  4820.2      .1       0  4855.5     .07       0  4993.7     .05       0
  5001.2     .07       0  5109.1      .1       0
Bank Sta=4993.7,5001.2
XS Rating Curve= 0 ,0
Exp/Cntr=0.3,0.1

Type RM Length L Ch R = 1 ,7386    ,466,466,466
BEGIN DESCRIPTION:
Frank Baker Creek 16.0
END DESCRIPTION:
XS GIS Cut Line= 3
      1835174.98     13900224.98        1835575.       13900625.
        1835575.     13900774.98
#Sta/Elev= 30
  4433.9 2029.95  4504.6 2024.31  4532.9 2023.37  4603.6 2014.49  4660.2 2009.84
  4688.5 2008.36  4740.8 2007.85  4872.3 2007.88  4886.5  2005.7  4900.6 2001.31
  4928.9  2005.6    4943 2004.57  4963.6 2004.83  4971.3 2005.05  4985.5 2003.76
  4996.1 2000.91  5005.8 2000.14  5006.3 1999.64  5013.5 2000.14  5019.6  2000.9
  5029.6 2005.96  5049.6 2003.63  5059.6 2001.41  5069.6 2002.82  5079.6 2019.18
  5089.6 2027.77  5109.6 2035.88  5119.6 2040.86  5147.1 2049.39  5149.6 2049.39
#Mann= 5 ,-1 , 0
  4433.9      .1       0  4740.8     .07       0  4963.6      .1       0
  5005.8     .05       0  5013.5      .1       0
Bank Sta=5005.8,5013.5
XS Rating Curve= 0 ,0
Exp/Cntr=0.3,0.1

Type RM Length L Ch R = 1 ,6920    ,460,460,460
BEGIN DESCRIPTION:
Frank Baker Creek 15.0
END DESCRIPTION:
XS GIS Cut Line= 3
        1835125.     13900324.95        1835125.       13900675.
        1835325.       13900925.
#Sta/Elev= 30
  4645.6 2024.01    4692 2021.89  4705.6 2019.71  4715.6 2017.16  4735.6 2013.53
  4755.6 2008.98  4775.6 2005.76  4785.6 2005.22  4835.6 2004.73  4925.6 2002.01
  4955.6 1999.74  4965.6  2000.5  5005.4 1998.06  5005.9 1997.56  5012.6 1997.56
  5013.1 1998.06  5038.1 1998.79  5046.1 2001.72  5052.5 2002.44  5059.7 2005.74
  5066.9 2008.19  5096.7 2012.63  5130.9 2018.62  5145.3 2021.61  5159.7  2025.6
  5180.5  2028.6  5230.2 2037.47  5287.8 2050.65  5312.6 2054.02  5315.8 2054.02
#Mann= 5 ,-1 , 0
  4645.6      .1       0    4692     .07       0  5005.4     .05       0
  5013.1     .07       0  5096.7      .1       0
Bank Sta=5005.4,5013.1
XS Rating Curve= 0 ,0
Exp/Cntr=0.3,0.1

Type RM Length L Ch R = 1 ,6460    ,450,450,450
BEGIN DESCRIPTION:
Frank Baker Creek 14.0
END DESCRIPTION:
XS GIS Cut Line= 3
      1834575.03     13900425.03        1834725.       13900575.
        1835075.     13900975.01
#Sta/Elev= 30
  4773.7 2032.61  4816.1 2027.46  4830.2 2024.76  4840.8 2020.52  4879.7 2007.95
  4899.5 2005.24  4929.2 2002.88  4957.5 2004.26  4989.1 2002.64  4992.9 1999.98
  4999.5 2000.51  5007.1 1998.27  5013.8 1998.72  5017.3 1997.59  5017.8 1997.09
  5025.5 1997.59  5113.4 1997.85  5170.4  2000.3  5226.4 1999.43  5262.5 2000.02
  5276.7 1999.18  5297.6    2000    5326 2004.18    5383  2008.7  5403.9 2011.93
  5446.6 2019.66  5481.7 2029.42  5503.5  2031.8    5514 2034.14  5517.3 2034.14
#Mann= 5 ,-1 , 0
  4773.7     .07       0  4840.8      .1       0  4899.5     .07       0
  5017.3     .05       0  5025.5     .07       0
Bank Sta=5017.3,5025.5
XS Rating Curve= 0 ,0
Exp/Cntr=0.3,0.1

Type RM Length L Ch R = 1 ,6010    ,450,450,450
BEGIN DESCRIPTION:
Frank Baker Creek 13.0
END DESCRIPTION:
XS GIS Cut Line= 3
      1834324.96     13900824.98        1834425.       13900875.
      1834824.98     13901274.98
#Sta/Elev= 30
  4888.4 2019.08  4933.2 2014.87  4941.5  2013.1    4963 2004.52  4969.5 2001.03
  4977.9 1995.35  4986.3 1992.17  4991.9 1991.37  5003.8 1991.25  5010.2 1990.12
  5010.7 1989.62    5018 1989.62  5018.5 1990.12  5028.5 1990.16  5042.7    1993
    5071 1996.97  5085.1 1997.81  5155.8 1998.19  5169.9 1997.65  5184.1 1995.72
  5226.5 1993.61  5254.8  1994.9  5268.9 1997.77  5283.1 1999.23  5326.3 2000.74
  5353.8 2000.72  5394.9 2002.29  5452.8 2005.79    5475 2007.92  5565.9  2014.7
#Mann= 7 ,-1 , 0
  4888.4      .1       0    4963     .07       0  5010.2     .05       0
  5018.5     .07       0  5326.3      .1       0  5394.9     .07       0
    5475      .1       0
Bank Sta=5010.2,5018.5
XS Rating Curve= 0 ,0
Exp/Cntr=0.3,0.1

Type RM Length L Ch R = 1 ,5560    ,448,448,448
BEGIN DESCRIPTION:
Frank Baker Creek 12.0
END DESCRIPTION:
XS GIS Cut Line= 3
      1833975.02     13901374.99        1834275.       13901275.
      1834674.99       13901375.
#Sta/Elev= 30
  4684.2 2105.83  4694.7  2104.1  4715.8 2096.58  4736.9 2086.06  4842.3 2041.72
  4884.5 2026.99    4895 2024.16  4916.1 2016.56  4926.6 2014.13  4947.7 2006.22
  4979.3  1996.4  4989.9 1990.23  4997.8 1982.82    5003 1982.82  5006.5 1981.35
    5007 1980.85  5014.9 1981.35  5018.4 1983.41  5023.6  1983.8  5047.9 1989.88
  5059.7 1991.72    5093 1993.78  5175.6 1993.24  5224.6 1995.67  5258.1 1995.74
  5297.9 1997.58  5319.9  1998.9  5330.3 1998.57  5353.4 2001.93  5412.7 2007.46
#Mann= 6 ,-1 , 0
  4684.2      .1       0  5006.5     .05       0  5014.9      .1       0
  5047.9     .07       0    5093      .1       0  5297.9     .07       0
Bank Sta=5006.5,5014.9
XS Rating Curve= 0 ,0
Exp/Cntr=0.3,0.1

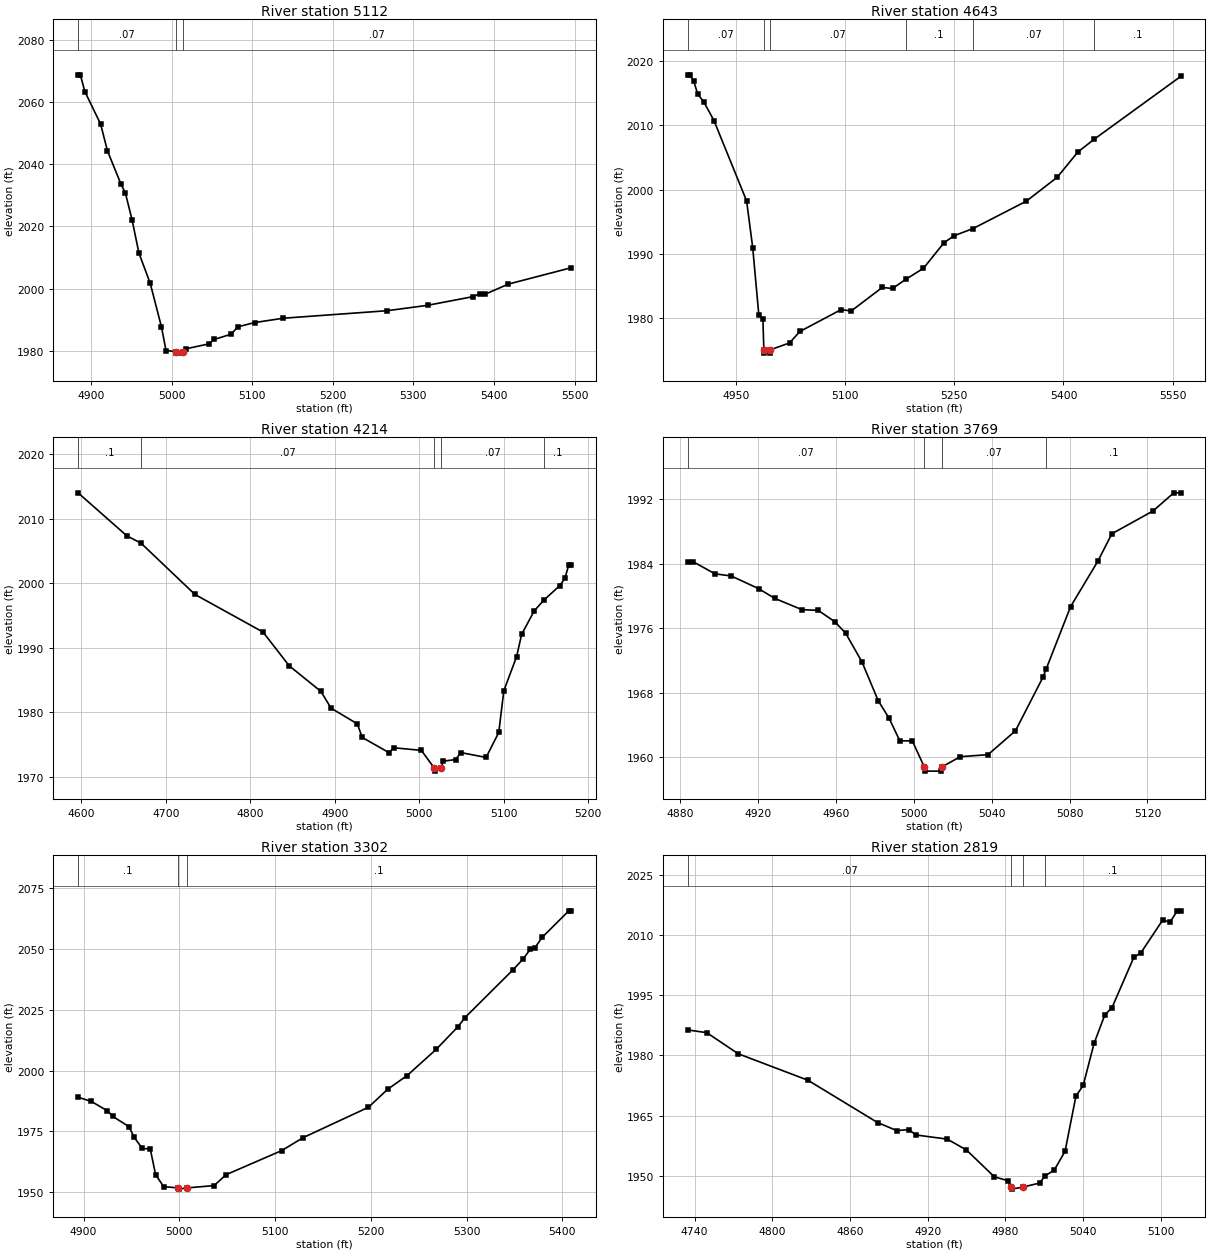
Type RM Length L Ch R = 1 ,5112    ,469,469,469
BEGIN DESCRIPTION:
Frank Baker Creek 11.0
END DESCRIPTION:
XS GIS Cut Line= 3
      1834174.96     13901775.02        1834275.       13901725.
      1834675.04     13901424.97
#Sta/Elev= 30
  4883.9  2068.7  4886.7  2068.7  4892.3 2063.34  4911.9 2052.87  4920.3 2044.31
  4937.1 2033.61  4942.6 2030.74    4951 2022.01  4959.4 2011.45  4973.4 2001.75
  4987.4 1987.71    4993 1980.14    5005  1979.8  5005.5  1979.3    5013  1979.3
  5013.5  1979.8  5017.6 1980.68  5045.8 1982.24    5053 1983.72  5073.9 1985.38
  5082.2 1987.75    5103 1989.12  5138.5 1990.51  5267.6 1992.93  5317.6 1994.66
  5373.9 1997.44  5382.2 1998.39  5388.5 1998.16  5417.6 2001.46  5495.8 2006.73
#Mann= 3 ,-1 , 0
  4883.9     .07       0    5005     .05       0  5013.5     .07       0
Bank Sta=5005,5013.5
XS Rating Curve= 0 ,0
Exp/Cntr=0.3,0.1

Type RM Length L Ch R = 1 ,4643    ,429,429,429
BEGIN DESCRIPTION:
Frank Baker Creek 10.0
END DESCRIPTION:
XS GIS Cut Line= 3
      1834575.02     13902074.96        1834625.       13901975.
      1835024.97     13901575.03
#Sta/Elev= 30
  4883.7 2017.86  4886.4 2017.86    4892 2016.91  4897.6 2014.85    4906 2013.64
    4920 2010.71  4964.7 1998.24  4973.1 1990.96  4981.5 1980.47  4987.1  1979.8
  4988.4 1975.05  4988.9 1974.55  4996.4 1974.55  4996.9 1975.05  5023.7 1976.14
  5037.9 1977.92  5094.4 1981.31  5108.6 1981.12    5151 1984.77  5165.2 1984.61
    5183 1986.01  5207.6 1987.75  5235.9 1991.73    5250 1992.84  5275.5 1993.92
    5349  1998.2  5391.4 2001.92  5419.7 2005.84  5442.2 2007.84  5561.1 2017.62
#Mann= 6 ,-1 , 0
  4883.7     .07       0  4988.4     .05       0  4996.9     .07       0
    5183      .1       0  5275.5     .07       0  5442.2      .1       0
Bank Sta=4988.4,4996.9
XS Rating Curve= 0 ,0
Exp/Cntr=0.3,0.1

Type RM Length L Ch R = 1 ,4214    ,445,445,445
BEGIN DESCRIPTION:
Frank Baker Creek 9.0
END DESCRIPTION:
XS GIS Cut Line= 3
      1834675.02     13902274.99        1835025.       13902075.
      1835175.03     13901974.98
#Sta/Elev= 30
  4596.3 2013.99  4653.9 2007.33  4670.9 2006.17  4734.5 1998.24  4815.1  1992.4
  4846.1 1987.17  4883.5 1983.21  4895.7 1980.59  4926.7 1978.17  4932.4 1976.07
  4964.1 1973.71  4969.9 1974.46  5002.4 1974.06  5017.6 1971.34  5018.1 1970.84
  5026.2 1971.34  5027.9 1972.38    5043 1972.63    5049 1973.72    5079 1972.96
    5094 1976.83    5100  1983.3  5115.1 1988.59  5121.1 1992.06  5136.1 1995.71
  5147.3 1997.34  5166.1 1999.59  5172.2 2000.71  5176.7 2002.76  5179.7 2002.76
#Mann= 5 ,-1 , 0
  4596.3      .1       0  4670.9     .07       0  5017.6     .05       0
  5026.2     .07       0  5147.3      .1       0
Bank Sta=5017.6,5026.2
XS Rating Curve= 0 ,0
Exp/Cntr=0.3,0.1

Type RM Length L Ch R = 1 ,3769    ,467,467,467
BEGIN DESCRIPTION:
Frank Baker Creek 8.0
END DESCRIPTION:
XS GIS Cut Line= 3
      1835174.97     13902425.02        1835275.       13902375.
      1835375.03     13902274.97
#Sta/Elev= 30
  4883.8 1984.24  4886.6 1984.24  4897.8 1982.74  4906.2 1982.47  4920.2 1980.91
  4928.6 1979.69  4942.5  1978.3  4950.9 1978.21  4959.3 1976.82  4964.9 1975.41
  4973.3 1971.85  4981.7 1967.02  4987.3 1964.84  4992.8 1962.05  4999.2 1962.05
  5005.4  1958.8  5005.9  1958.3  5013.7  1958.3  5014.2  1958.8  5023.9 1960.09
  5038.1 1960.34  5052.2  1963.3  5066.3 1969.92  5067.9 1970.91  5080.5 1978.67
  5094.6 1984.34  5101.7  1987.7  5122.9 1990.53  5133.5 1992.77  5137.1 1992.77
#Mann= 4 ,-1 , 0
  4883.8     .07       0  5005.4     .05       0  5014.2     .07       0
  5067.9      .1       0
Bank Sta=5005.4,5014.2
XS Rating Curve= 0 ,0
Exp/Cntr=0.3,0.1

Type RM Length L Ch R = 1 ,3302    ,483,483,483
BEGIN DESCRIPTION:
Frank Baker Creek 7.0
END DESCRIPTION:
XS GIS Cut Line= 3
      1835525.03     13902724.99        1835625.       13902675.
      1836025.02       13902625.
#Sta/Elev= 30
  4894.3 1989.06  4908.2 1987.31    4925 1983.46  4930.6 1981.15  4947.4 1976.99
    4953 1972.55  4961.3 1968.05  4969.7 1967.78  4975.3 1957.21  4983.7 1952.37
  4998.8 1951.84  4999.3 1951.34  5007.7 1951.84  5036.3 1952.78  5048.9 1957.27
  5106.8 1967.13  5129.5 1972.51  5197.5 1984.93  5217.7 1992.35  5237.9 1997.95
  5268.1 2008.64  5290.8  2017.9  5298.3 2021.72  5348.7 2041.43  5358.8 2045.67
  5366.4 2049.72  5371.4 2050.45    5379 2054.68  5406.7 2065.53  5409.2 2065.53
#Mann= 3 ,-1 , 0
  4894.3      .1       0  4998.8     .05       0  5007.7      .1       0
Bank Sta=4998.8,5007.7
XS Rating Curve= 0 ,0
Exp/Cntr=0.3,0.1

Type RM Length L Ch R = 1 ,2819    ,437,437,437
BEGIN DESCRIPTION:
Frank Baker Creek 6.0
END DESCRIPTION:
XS GIS Cut Line= 3
      1835575.02     13902975.01        1835825.       13903075.
      1835924.96     13903124.98
#Sta/Elev= 30
  4734.6 1986.37  4749.4 1985.68  4773.6 1980.43  4827.5 1973.82  4881.3 1963.27
  4896.1 1961.26  4905.6 1961.49  4910.9 1960.17  4935.2 1959.12    4950 1956.42
  4971.5 1949.74  4982.3 1948.72  4984.5 1947.15    4985 1946.65  4993.5 1947.15
  5006.6 1948.17  5010.7 1949.96  5017.8 1951.37  5026.2 1956.08  5034.6 1969.85
  5040.2 1972.51  5048.6 1982.99  5056.9  1990.1  5062.5 1991.95  5079.3 2004.45
  5084.9 2005.65  5101.7 2013.81  5107.3 2013.23  5112.9 2016.08  5115.6 2016.08
#Mann= 4 ,-1 , 0
  4734.6     .07       0  4984.5     .05       0  4993.5     .07       0
  5010.7      .1       0
Bank Sta=4984.5,4993.5
XS Rating Curve= 0 ,0
Exp/Cntr=0.3,0.1

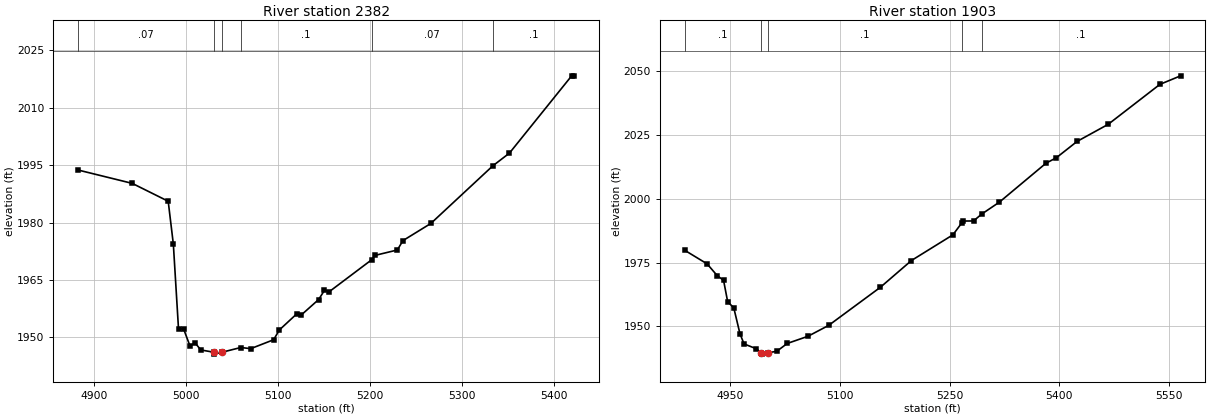
Type RM Length L Ch R = 1 ,2382    ,479,479,479
BEGIN DESCRIPTION:
Frank Baker Creek 5.0
END DESCRIPTION:
XS GIS Cut Line= 3
      1835474.99     13903374.99        1835575.       13903425.
      1835974.99     13903275.01
#Sta/Elev= 30
  4882.6 1993.73  4941.3 1990.25  4980.4 1985.58    4986 1974.36  4991.6 1952.26
  4997.1 1952.26  5004.2 1947.69  5009.5 1948.64  5015.8 1946.74    5030 1946.15
  5030.5 1945.65    5039 1946.15  5059.3 1947.38  5070.1 1947.08    5095 1949.41
  5101.2 1951.96  5119.9 1956.12  5125.2 1955.91  5143.9 1959.91  5150.2  1962.3
  5155.5 1961.97  5201.5 1970.29  5205.3 1971.45  5229.4 1972.85  5235.6 1975.31
  5265.9 1979.79  5333.2 1994.83  5351.3 1998.16  5418.9 2018.34  5421.6 2018.34
#Mann= 6 ,-1 , 0
  4882.6     .07       0    5030     .05       0    5039     .07       0
  5059.3      .1       0  5201.5     .07       0  5333.2      .1       0
Bank Sta=5030,5039
XS Rating Curve= 0 ,0
Exp/Cntr=0.3,0.1

Type RM Length L Ch R = 1 ,1903    ,446,446,446
BEGIN DESCRIPTION:
Frank Baker Creek 4.0
END DESCRIPTION:
XS GIS Cut Line= 3
        1835675.       13903875.        1835775.       13903825.
      1836175.01     13903424.99
#Sta/Elev= 30
  4888.2 1979.79  4918.9 1974.45  4932.9 1969.78  4941.3 1968.06  4946.9  1959.7
  4955.3 1957.24  4963.7 1947.15  4969.3 1943.15    4986 1941.27  4992.7 1939.66
  4993.2 1939.16  5001.8 1939.66  5014.1 1940.29  5028.3 1943.33  5056.6 1946.14
  5084.9  1950.4  5155.6 1965.32    5198 1975.78  5254.6 1985.82  5266.6 1990.42
  5268.7 1991.22  5282.8 1991.25  5293.8 1993.91  5318.2 1998.63  5381.8 2013.84
    5396 2015.99  5424.3 2022.37  5466.7 2029.04  5537.4 2044.68  5565.7 2048.02
#Mann= 5 ,-1 , 0
  4888.2      .1       0  4992.7     .05       0  5001.8      .1       0
  5266.6     .07       0  5293.8      .1       0
Bank Sta=4992.7,5001.8
XS Rating Curve= 0 ,0
Exp/Cntr=0.3,0.1