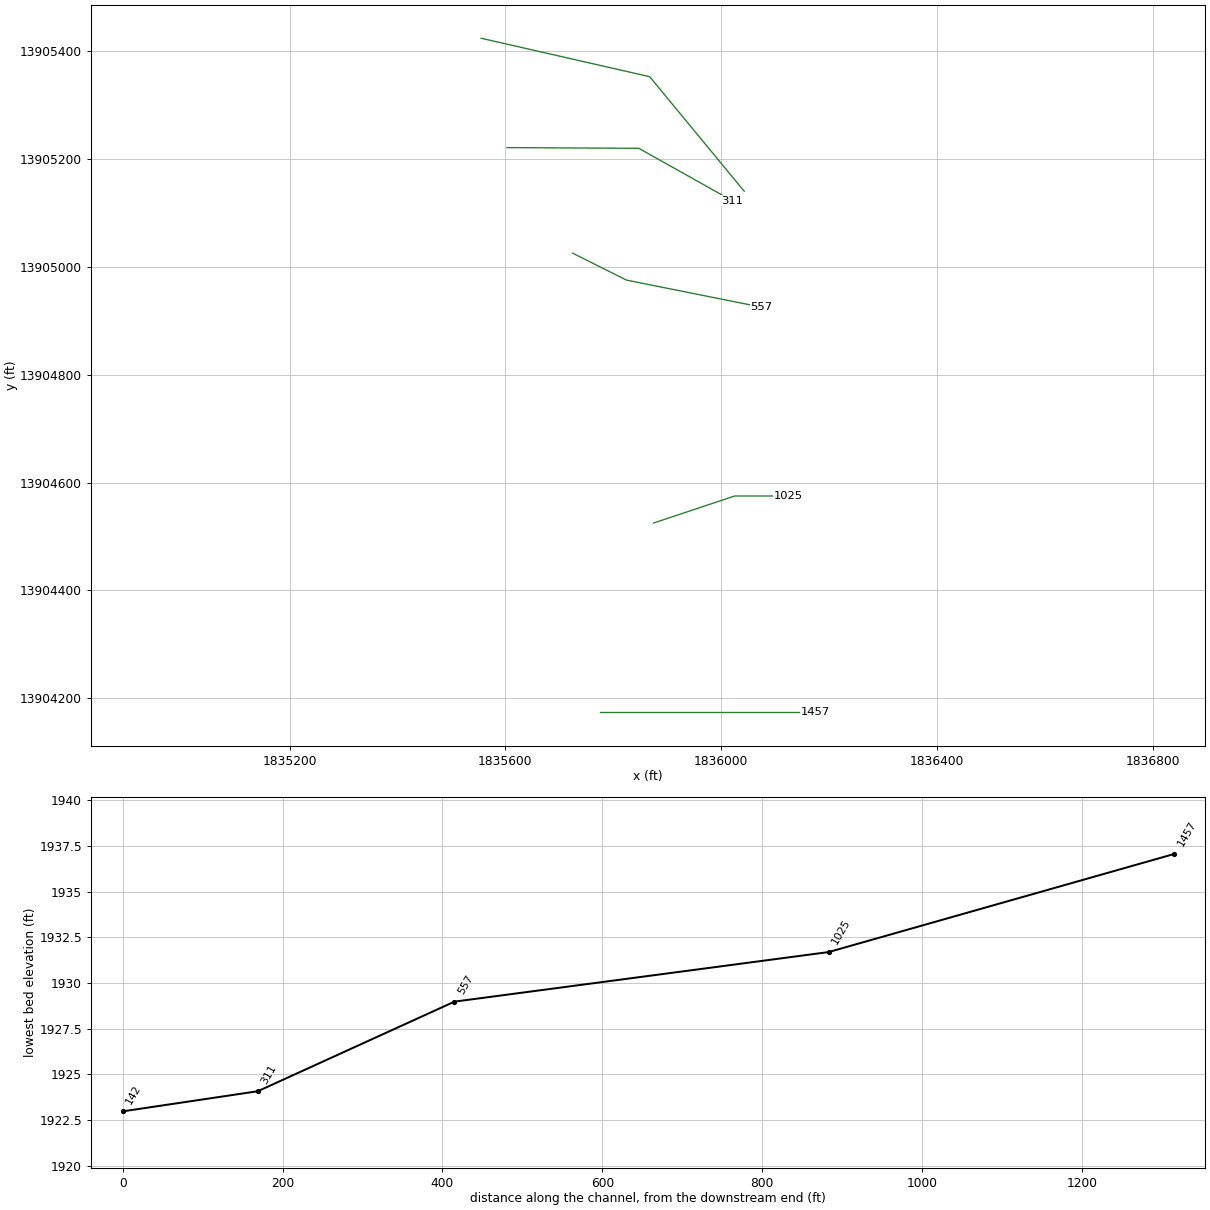
HEC-RAS study Frank Baker Creek.prj: Frank Baker Creek Base Level Engineering

--- Frank Baker Creek.g01 (geometry) --- (continued)

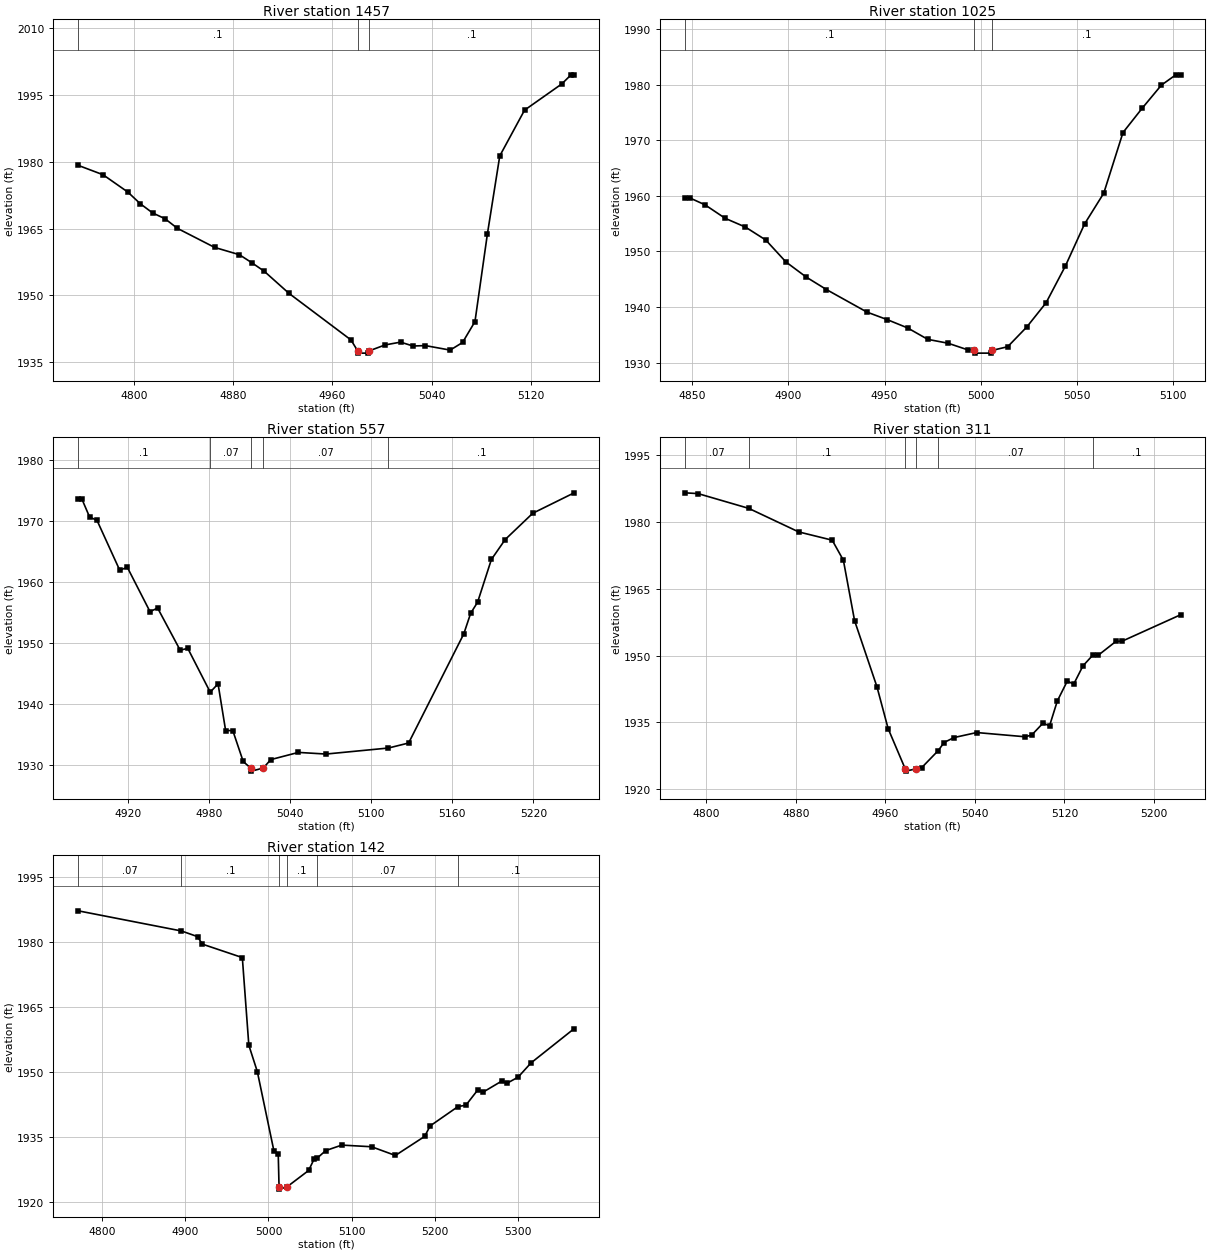
Type RM Length L Ch R = 1 ,1457    ,432,432,432
BEGIN DESCRIPTION:
Frank Baker Creek 3.0
END DESCRIPTION:
XS GIS Cut Line= 3
      1835774.96       13904175.        1836025.       13904175.
      1836174.96       13904175.
#Sta/Elev= 30
    4755 1979.21    4775 1977.11    4795 1973.22    4805 1970.61    4815 1968.53
    4825 1967.23    4835 1965.07    4865 1960.79    4885 1959.15    4895 1957.35
    4905 1955.44    4925 1950.47    4975 1940.01  4980.4 1937.55  4980.9 1937.05
  4989.1 1937.05  4989.6 1937.55  5002.5 1938.89    5015 1939.52    5025 1938.65
    5035 1938.74    5055 1937.73    5065 1939.44    5075 1944.13    5085 1963.76
    5095 1981.33    5115 1991.61    5145 1997.49  5152.5 1999.54    5155 1999.54
#Mann= 3 ,-1 , 0
    4755      .1       0  4980.4     .05       0  4989.6      .1       0
Bank Sta=4980.4,4989.6
XS Rating Curve= 0 ,0
Exp/Cntr=0.3,0.1

Type RM Length L Ch R = 1 ,1025    ,468,468,468
BEGIN DESCRIPTION:
Frank Baker Creek 2.0
END DESCRIPTION:
XS GIS Cut Line= 3
      1835874.98     13904524.99        1836025.       13904575.
      1836124.97       13904575.
#Sta/Elev= 30
    4846 1959.62  4848.7 1959.62  4856.6 1958.38  4867.1 1955.95  4877.6 1954.38
  4888.2 1952.05  4898.7  1948.1  4909.3 1945.37  4919.8 1943.13  4940.9 1939.07
  4951.4 1937.72    4962 1936.23  4972.5 1934.17  4983.1 1933.47  4993.6 1932.25
  4996.8 1932.19  4997.3 1931.69  5005.6 1931.69  5006.1 1932.19  5014.1 1932.84
  5024.1 1936.42  5034.1 1940.76  5044.1 1947.35  5054.1 1954.93  5064.1 1960.48
  5074.1 1971.39  5084.1 1975.77  5094.1 1979.93  5101.6 1981.78  5104.1 1981.78
#Mann= 3 ,-1 , 0
    4846      .1       0  4996.8     .05       0  5006.1      .1       0
Bank Sta=4996.8,5006.1
XS Rating Curve= 0 ,0
Exp/Cntr=0.3,0.1

Type RM Length L Ch R = 1 ,557     ,246,246,246
BEGIN DESCRIPTION:
Frank Baker Creek 1.0
END DESCRIPTION:
XS GIS Cut Line= 3
      1835725.03     13905024.99        1835825.       13904975.
      1836074.98       13904925.
#Sta/Elev= 30
  4883.4 1973.56  4886.2 1973.56  4891.8 1970.66  4897.3  1970.1  4914.1 1961.93
  4919.7 1962.41  4936.5 1955.13  4942.1 1955.73  4958.8 1948.81  4964.4 1949.12
    4981 1941.93  4986.8  1943.3  4992.4 1935.63  4997.7 1935.63  5005.4 1930.56
  5010.9 1929.48  5011.4 1928.98  5020.2 1929.48  5025.8 1930.87  5046.2 1932.05
  5066.6 1931.78  5112.8 1932.77  5127.7 1933.59  5168.5 1951.49  5173.6 1954.88
  5178.7 1956.68  5188.9 1963.69  5199.1 1966.96  5219.5 1971.27  5250.1 1974.62
#Mann= 5 ,-1 , 0
  4883.4      .1       0    4981     .07       0  5010.9     .05       0
  5020.2     .07       0  5112.8      .1       0
Bank Sta=5010.9,5020.2
XS Rating Curve= 0 ,0
Exp/Cntr=0.3,0.1

Type RM Length L Ch R = 1 ,311     ,169,169,169
BEGIN DESCRIPTION:
Frank Baker Creek 0.1
END DESCRIPTION:
XS GIS Cut Line= 3
      1835603.11     13905220.63      1835847.56     13905219.29
      1836021.12     13905122.03
#Sta/Elev= 30
  4780.5 1986.55  4792.4 1986.38  4837.8 1983.06  4882.4 1977.78  4912.4 1975.92
  4922.4 1971.41  4932.4 1957.85  4952.4 1943.02  4962.4 1933.62  4977.7 1924.58
  4978.2 1924.08  4987.1 1924.58  4992.4 1924.86  5007.2 1928.69  5012.4  1930.5
  5021.2 1931.61  5041.6 1932.74    5085 1931.79  5090.8 1932.19  5100.9 1934.86
  5106.7 1934.24  5113.7 1939.85  5122.6  1944.3  5128.3  1943.6  5136.6 1947.71
  5145.7  1950.2    5150 1950.04    5166 1953.19  5171.7 1953.26  5223.9 1959.18
#Mann= 6 ,-1 , 0
  4780.5     .07       0  4837.8      .1       0  4977.7     .05       0
  4987.1      .1       0  5007.2     .07       0  5145.7      .1       0
Bank Sta=4977.7,4987.1
XS Rating Curve= 0 ,0
Exp/Cntr=0.3,0.1

Type RM Length L Ch R = 1 ,142     ,0,0,0
BEGIN DESCRIPTION:
Frank Baker Creek 0.0
END DESCRIPTION:
XS GIS Cut Line= 3
      1835555.25     13905423.23      1835867.68     13905352.03
      1836042.88     13905139.85
#Sta/Elev= 30
  4771.5  1987.2  4895.5 1982.55  4914.8 1981.25  4920.5 1979.52  4968.6 1976.41
  4976.4 1956.19  4986.6  1950.1  5006.5 1931.82  5011.7 1931.19  5012.7 1923.48
  5013.2 1922.98  5022.1 1923.48  5048.2 1927.28  5054.7 1929.88  5058.1 1930.06
  5068.7 1931.87    5088 1933.14  5123.8 1932.76  5152.4 1930.75  5187.6 1935.15
  5194.1 1937.56  5227.6 1942.03  5237.1 1942.35  5251.4 1945.88  5257.9 1945.38
  5280.1 1947.91  5286.6 1947.43  5299.8 1948.82  5315.2 1952.09  5367.1 1960.01
#Mann= 6 ,-1 , 0
  4771.5     .07       0  4895.5      .1       0  5012.7     .05       0
  5022.1      .1       0  5058.1     .07       0  5227.6      .1       0
Bank Sta=5012.7,5022.1
XS Rating Curve= 0 ,0
Exp/Cntr=0.3,0.1

Chan Stop Cuts=-1
Use User Specified Reach Order=0
Composite Channel Slope=5