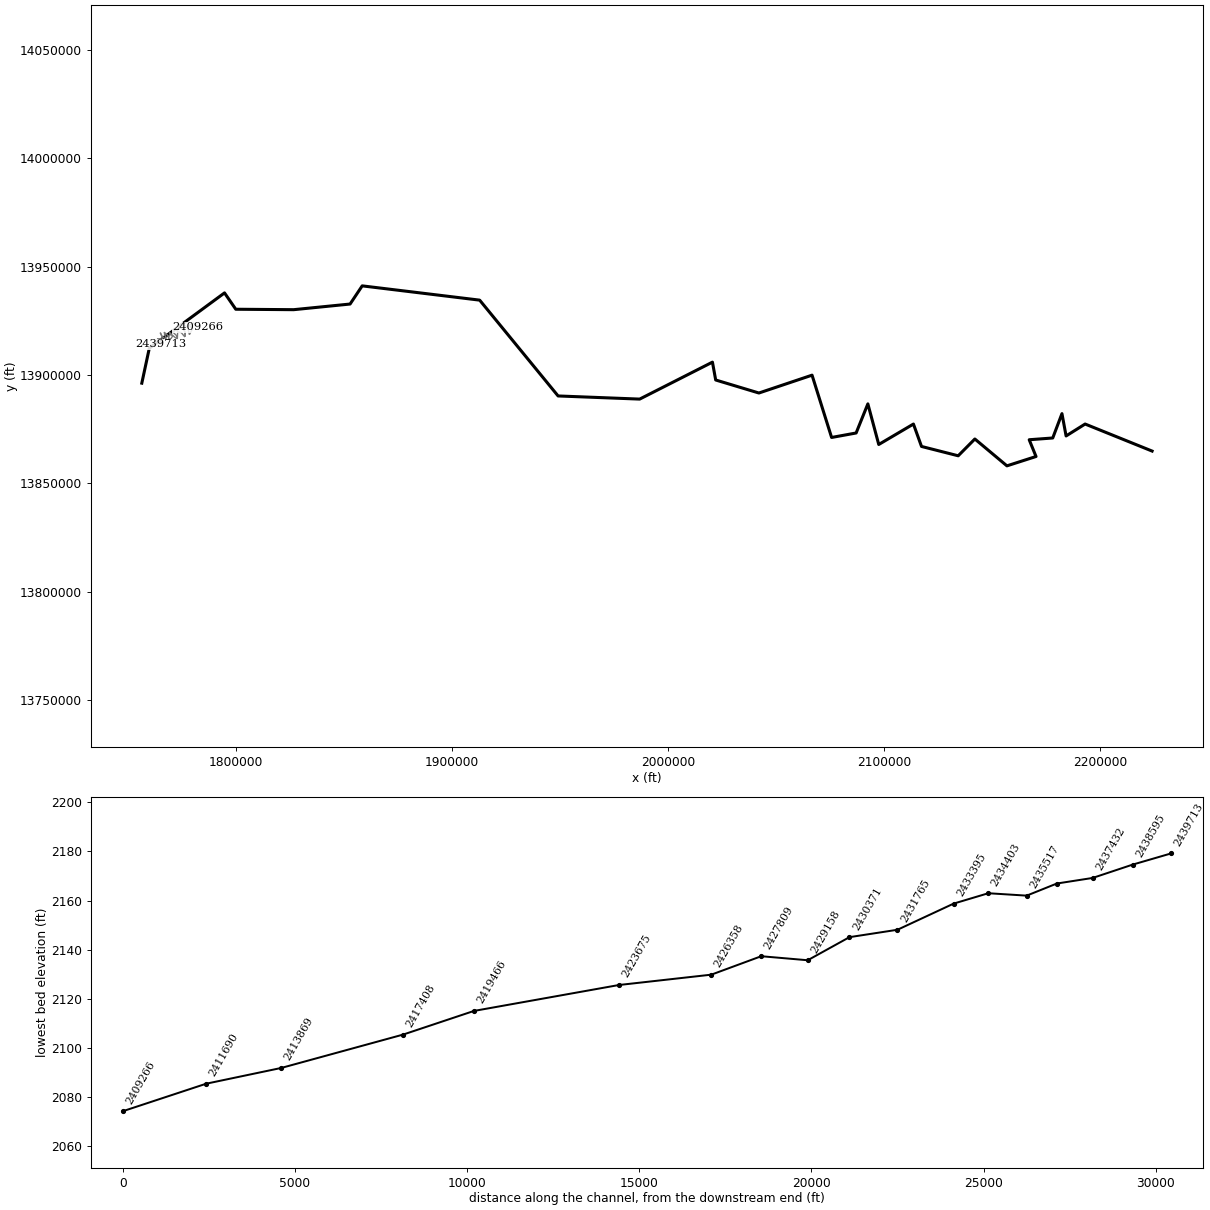
--- Guadalupe River.prj (project) ---

Proj Title=Guadalupe River Base Level Engineering
Current Plan=p01
Default Exp/Contr=0.3,0.1
English Units
Geom File=g01
Flow File=f01
Plan File=p01
Y Axis Title=Elevation
X Axis Title(PF)=Main Channel Distance
X Axis Title(XS)=Station
BEGIN DESCRIPTION:
Guadalupe River
END DESCRIPTION:
DSS Export Rating Curves= 0
DSS Export Rating Curve Sorted= 0
DSS Export Volume Flow Curves= 0
DXF OffsetX= 0
DXF OffsetY= 0
DXF ScaleX= 1
DXF ScaleY= 10

--- Guadalupe River.p01 (plan) ---

Plan Title=Multiple Run
Short Identifier=Multiple
Geom File=g01
Flow File=f01
Subcritical Flow
K Sum by GR= 0
Std Step Tol= 0.01
Critical Tol= 0.01
Num of Std Step Trials= 20
Max Error Tol= 0.3
Flow Tol Ratio= 0.001
Split Flow NTrial= 30
Split Flow Tol= 0.02
Split Flow Ratio= 0.02
Log Output Level= 0
Friction Slope Method= 1
Unsteady Friction Slope Method= 2
Unsteady Bridges Friction Slope Method= 1
Parabolic Critical Depth
Global Vel Dist=  1 , 1 , 1
Global Log Level= 0
CheckData=True
Encroach Param= -1, 0, 0, 0
BEGIN DESCRIPTION:
Multiple Run
END DESCRIPTION:

--- Guadalupe River.f01 (steady flow) ---

Flow Title=Multiple
Number of Profiles=7
Profile Names=10-year,25-year,50-year,1pct_min,100-year,1pct_plu,500-year
River Rch & RM= Guadalupe River,Reach-1,2439713
    4243    7665   11086    7700   15363   30653   29224
River Rch & RM= Guadalupe River,Reach-1,2436393
    6085   11146   16272   11398   22742   45376   43998
River Rch & RM= Guadalupe River,Reach-1,2434403
    6379   11689   17069   11957   23858   47603   46165
River Rch & RM= Guadalupe River,Reach-1,2431765
    6388   11698   17075   11956   23855   47597   46113
River Rch & RM= Guadalupe River,Reach-1,2429158
    6951   12767   18672   13098   26133   52143   50698
River Rch & RM= Guadalupe River,Reach-1,2427809
    6876   12604   18408   12893   25725   51329   49760
River Rch & RM= Guadalupe River,Reach-1,2423675
    6817   12479   18208   12740   25420   50719   49067
River Rch & RM= Guadalupe River,Reach-1,2419466
    6818   12447   18127   12658   25256   50393   48554
River Rch & RM= Guadalupe River,Reach-1,2411690
    6862   12525   18239   12734   25407   50694   48826
River Rch & RM= Guadalupe River,Reach-1,2406337
   10765   19907   29254   20594   41090   81986   80249
River Rch & RM= Guadalupe River,Reach-1,2404689
   10721   19814   29106   20480   40864   81534   79739
River Rch & RM= Guadalupe River,Reach-1,2402432
   10655   19670   28873   20301   40505   80818   78911
River Rch & RM= Guadalupe River,Reach-1,2400400
   10775   19893   29202   20533   40968   81742   79817
River Rch & RM= Guadalupe River,Reach-1,2399030
   10888   20102   29509   20748   41397   82598   80647
River Rch & RM= Guadalupe River,Reach-1,2396059
   10922   20157   29582   20793   41488   82780   80778
River Rch & RM= Guadalupe River,Reach-1,2394138
   10976   20242   29690   20857   41615   83033   80928
River Rch & RM= Guadalupe River,Reach-1,2390658
   10940   20160   29555   20750   41402   82608   80423
River Rch & RM= Guadalupe River,Reach-1,2387157
   15213   28276   41709   29450   58761  117244  115399
River Rch & RM= Guadalupe River,Reach-1,2386265
   15198   28238   41643   29396   58653  117027  115127
River Rch & RM= Guadalupe River,Reach-1,2384529
   15208   28255   41667   29412   58685  117092  115183
River Rch & RM= Guadalupe River,Reach-1,2382576
   16356   30437   44936   31753   63356  126413  124603
River Rch & RM= Guadalupe River,Reach-1,2378719
   16480   30656   45246   31962   63773  127243  125337
River Rch & RM= Guadalupe River,Reach-1,2375890
   16562   30779   45400   32049   63946  127589  125504
River Rch & RM= Guadalupe River,Reach-1,2368681
   16500   30633   45153   31852   63552  126803  124550
River Rch & RM= Guadalupe River,Reach-1,2362954
   19548   36437   53864   38101   76021  151682  149765
River Rch & RM= Guadalupe River,Reach-1,2361358
   19846   36974   54640   38636   77088  153811  151749
River Rch & RM= Guadalupe River,Reach-1,2357626
   19837   36945   54586   38588   76993  153621  151488
River Rch & RM= Guadalupe River,Reach-1,2356242
   19803   36859   54436   38465   76747  153131  150870
River Rch & RM= Guadalupe River,Reach-1,2353952
   20452   38079   56251   39756   79323  158270  155987
River Rch & RM= Guadalupe River,Reach-1,2349984
   20398   37949   56030   39577   78967  157560  155116
River Rch & RM= Guadalupe River,Reach-1,2344003
   20447   38023   56121   39629   79070  157765  155213
River Rch & RM= Guadalupe River,Reach-1,2340547
   20479   38084   56213   39695   79201  158027  155477
River Rch & RM= Guadalupe River,Reach-1,2337438
   21949   40698   59970   42275   84349  168298  164913
River Rch & RM= Guadalupe River,Reach-1,2329861
   21781   40337   59387   41826   83453  166510  162866
River Rch & RM= Guadalupe River,Reach-1,2318967
   22121   40961   60301   42465   84729  169056  165316
River Rch & RM= Guadalupe River,Reach-1,2313796
   26401   49034   72354   51065  101887  203292  199605
River Rch & RM= Guadalupe River,Reach-1,2311134
   26327   48877   72102   50872  101502  202523  198733
River Rch & RM= Guadalupe River,Reach-1,2307054
   26462   49113   72437   51097  101952  203421  199528
River Rch & RM= Guadalupe River,Reach-1,2301489
   26459   49103   72417   51079  101915  203348  199423
River Rch & RM= Guadalupe River,Reach-1,2299536
   26484   49125   72425   51067  101892  203301  199237
River Rch & RM= Guadalupe River,Reach-1,2293902
   26647   49418   72848   51359  102474  204462  200318
River Rch & RM= Guadalupe River,Reach-1,2289569
   26664   49440   72871   51367  102491  204496  200291
River Rch & RM= Guadalupe River,Reach-1,2285258
   26617   49335   72699   51233  102222  203961  199665
River Rch & RM= Guadalupe River,Reach-1,2283234
   29191   54016   79534   56005  111745  222960  217783
River Rch & RM= Guadalupe River,Reach-1,2279832
   29214   54055   79589   56041  111817  223104  217906
River Rch & RM= Guadalupe River,Reach-1,2275967
   29295   54191   79776   56163  112060  223590  218302
River Rch & RM= Guadalupe River,Reach-1,2270284
   38922   72238  106637   75268  150180  299648  293919
River Rch & RM= Guadalupe River,Reach-1,2266559
   39266   72840  107489   75843  151327  301936  295946
River Rch & RM= Guadalupe River,Reach-1,2262965
   39572   73426  108375   76483  152603  304483  298556
River Rch & RM= Guadalupe River,Reach-1,2260469
   39758   73757  108851   76809  153255  305783  299750
River Rch & RM= Guadalupe River,Reach-1,2256369
   40164   74467  109858   77489  154611  308489  302152
River Rch & RM= Guadalupe River,Reach-1,2250737
   40145   74415  109763   77409  154451  308170  301734
River Rch & RM= Guadalupe River,Reach-1,2247469
   40281   74663  110124   77660  154952  309169  302684
River Rch & RM= Guadalupe River,Reach-1,2243698
   40305   74698  110166   77683  154998  309263  302723
River Rch & RM= Guadalupe River,Reach-1,2240942
   40126   74320  109563   77223  154080  307431  300662
River Rch & RM= Guadalupe River,Reach-1,2238829
   50617   93949  138767   97990  195516  390106  382766
River Rch & RM= Guadalupe River,Reach-1,2237225
   51428   95488  141079   99651  198831  396720  389465
River Rch & RM= Guadalupe River,Reach-1,2231760
   51259   95130  140505   99213  197956  394974  387493
River Rch & RM= Guadalupe River,Reach-1,2229567
   51252   95110  140467   99180  197891  394844  387317
River Rch & RM= Guadalupe River,Reach-1,2226352
   53301   98671  145523  102609  204732  408493  399407
River Rch & RM= Guadalupe River,Reach-1,2218489
   54681  101213  149267  105245  209991  418987  409610
River Rch & RM= Guadalupe River,Reach-1,2215484
   55151  102060  150497  106097  211691  422379  412799
River Rch & RM= Guadalupe River,Reach-1,2213227
   55190  102074  150460  106029  211556  422110  412207
River Rch & RM= Guadalupe River,Reach-1,2210090
   55036  101730  149894  105586  210672  420346  410140
River Rch & RM= Guadalupe River,Reach-1,2204225
   55172  101980  150260  105843  211184  421367  411126
River Rch & RM= Guadalupe River,Reach-1,2197577
   56805  104966  154640  108913  217310  433591  422903
River Rch & RM= Guadalupe River,Reach-1,2185637
   57391  105993  156101  109903  219286  437532  426434
River Rch & RM= Guadalupe River,Reach-1,2177328
   57801  106676  157034  110508  220493  439941  428363
River Rch & RM= Guadalupe River,Reach-1,2173674
   58518  107958  158885  111784  223039  445021  433087
River Rch & RM= Guadalupe River,Reach-1,2167729
   56931  104965  154430  108645  216775  432523  421014
River Rch & RM= Guadalupe River,Reach-1,2159546
   57084  105223  154787  108879  217242  433454  421787
River Rch & RM= Guadalupe River,Reach-1,2156942
   59545  109498  160857  112998  225460  449852  436358
River Rch & RM= Guadalupe River,Reach-1,2145955
   64483  118602  174287  122471  244362  487566  473164
River Rch & RM= Guadalupe River,Reach-1,2138596
   64796  119172  175122  123056  245528  489894  475400
River Rch & RM= Guadalupe River,Reach-1,2134666
   64594  118731  174403  122499  244417  487677  472848
River Rch & RM= Guadalupe River,Reach-1,2124810
   64838  119125  174931  122834  245085  489009  473850
River Rch & RM= Guadalupe River,Reach-1,2115991
   64909  119252  175114  122959  245335  489509  474309
River Rch & RM= Guadalupe River,Reach-1,2113115
   68325  125516  184324  129434  258255  515287  499294
River Rch & RM= Guadalupe River,Reach-1,2109087
   51194   93216  136170   95359  190267  379633  366888
River Rch & RM= Guadalupe River,Reach-1,2099359
   53124   96524  140833   98508  196549  392167  377931
River Rch & RM= Guadalupe River,Reach-1,2095549
   54050   98177  143222  100163  199852  398757  384141
River Rch & RM= Guadalupe River,Reach-1,2091562
   53980   98030  142990   99987  199500  398054  383358
River Rch & RM= Guadalupe River,Reach-1,2085485
   54306   98584  143763  100502  200529  400108  385136
River Rch & RM= Guadalupe River,Reach-1,2073321
   54388   98682  143856  100532  200588  400226  384972
River Rch & RM= Guadalupe River,Reach-1,2067704
   54248   98372  143348  100136  199798  398650  383143
River Rch & RM= Guadalupe River,Reach-1,2060132
  115823  226286  347403  256123  511033 1019645 1091411
River Rch & RM= Guadalupe River,Reach-1,2056775
  105759  204587  311928  228334  455587  909015  959205
River Rch & RM= Guadalupe River,Reach-1,2048998
  115405  225156  345341  254354  507503 1012601 1081731
River Rch & RM= Guadalupe River,Reach-1,2043738
  109746  212788  324966  238284  475439  948626 1004383
River Rch & RM= Guadalupe River,Reach-1,2036431
  105932  204590  311596  227837  454595  907036  954947
River Rch & RM= Guadalupe River,Reach-1,2029723
  105251  203107  309160  225922  450773  899411  945795
River Rch & RM= Guadalupe River,Reach-1,2025614
  101408  194227  294124  213794  426576  851130  885490
River Rch & RM= Guadalupe River,Reach-1,2021457
   99814  190844  288654  209558  418124  834267  865796
River Rch & RM= Guadalupe River,Reach-1,2008426
   98983  187941  282962  204467  407966  813998  836515
River Rch & RM= Guadalupe River,Reach-1,2003595
   98455  186786  281065  202979  404997  808074  829461
River Rch & RM= Guadalupe River,Reach-1,1999284
   97420  184601  277546  200265  399582  797270  816965
River Rch & RM= Guadalupe River,Reach-1,1995821
   96852  183380  275559  198719  396496  791114  809733
River Rch & RM= Guadalupe River,Reach-1,1991221
   95663  180880  271543  195630  390333  778817  795578
River Rch & RM= Guadalupe River,Reach-1,1987517
   97650  183943  275492  198004  395071  788270  801066
River Rch & RM= Guadalupe River,Reach-1,1982220
   96458  181443  271480  194924  388925  776008  787012
River Rch & RM= Guadalupe River,Reach-1,1977619
   97612  183274  273890  196412  391893  781928  791003
River Rch & RM= Guadalupe River,Reach-1,1968469
   96516  180971  270192  193570  386223  770617  778035
River Rch & RM= Guadalupe River,Reach-1,1964388
   95866  179610  268013  191899  382890  763965  770440
River Rch & RM= Guadalupe River,Reach-1,1960389
   94898  177581  264761  189406  377915  754039  759104
River Rch & RM= Guadalupe River,Reach-1,1956307
   94150  175971  262145  187375  373863  745955  749685
River Rch & RM= Guadalupe River,Reach-1,1949277
   97606  182321  271524  194023  387126  772418  775753
River Rch & RM= Guadalupe River,Reach-1,1945539
   96550  180112  267990  191317  381728  761647  763493
River Rch & RM= Guadalupe River,Reach-1,1938719
   95579  178091  264766  188855  376815  751846  752389
River Rch & RM= Guadalupe River,Reach-1,1933707
   94693  176253  261841  186627  372370  742976  742386
River Rch & RM= Guadalupe River,Reach-1,1926018
   94210  175157  260012  185177  369476  737201  735437
River Rch & RM= Guadalupe River,Reach-1,1919985
   93581  173855  257942  183601  366332  730928  728375
River Rch & RM= Guadalupe River,Reach-1,1914747
   92049  170689  252915  179780  358709  715718  711298
River Rch & RM= Guadalupe River,Reach-1,1905654
   91600  169727  251358  178578  356310  710932  705780
River Rch & RM= Guadalupe River,Reach-1,1902852
   91538  169584  251119  178387  355930  710173  704863
River Rch & RM= Guadalupe River,Reach-1,1899796
   94259  174216  257621  182756  364646  727564  719844
River Rch & RM= Guadalupe River,Reach-1,1896605
   93817  173301  256168  181652  362444  723170  714918
River Rch & RM= Guadalupe River,Reach-1,1891406
   94164  173838  256858  182067  363272  724822  715952
River Rch & RM= Guadalupe River,Reach-1,1888839
   93674  172816  255229  180824  360792  719874  710373
River Rch & RM= Guadalupe River,Reach-1,1885278
   94229  173787  256615  181773  362684  723650  713819
River Rch & RM= Guadalupe River,Reach-1,1883136
   94070  173457  256092  181376  361892  722069  712049
River Rch & RM= Guadalupe River,Reach-1,1879904
   93516  172315  254282  180002  359151  716601  705940
River Rch & RM= Guadalupe River,Reach-1,1875755
   93363  171998  253779  179620  358389  715081  704241
River Rch & RM= Guadalupe River,Reach-1,1873525
   92867  170964  252130  178363  355882  710077  698607
River Rch & RM= Guadalupe River,Reach-1,1870036
   92521  170249  250995  177502  354164  706650  694777
River Rch & RM= Guadalupe River,Reach-1,1866208
   91711  168590  248378  175526  350220  698781  686058
River Rch & RM= Guadalupe River,Reach-1,1858221
   88137  162196  239079  169033  337265  672931  661569
River Rch & RM= Guadalupe River,Reach-1,1853667
   88106  162116  238937  168915  337030  672464  660974
River Rch & RM= Guadalupe River,Reach-1,1851499
   87949  161795  238432  168535  336271  670949  659300
River Rch & RM= Guadalupe River,Reach-1,1849137
   87791  161424  237804  168031  335267  668945  656863
River Rch & RM= Guadalupe River,Reach-1,1845013
   87597  160991  237089  167470  334147  666710  654229
River Rch & RM= Guadalupe River,Reach-1,1841592
   87192  160146  235741  166443  332097  662622  649628
River Rch & RM= Guadalupe River,Reach-1,1835774
   87213  160175  235774  166459  332129  662685  649634
River Rch & RM= Guadalupe River,Reach-1,1833922
   87065  159866  235281  166084  331381  661191  647954
River Rch & RM= Guadalupe River,Reach-1,1830661
   86657  159027  233957  165083  329384  657208  643537
River Rch & RM= Guadalupe River,Reach-1,1825499
   86503  158705  233442  164690  328599  655641  641770
River Rch & RM= Guadalupe River,Reach-1,1823371
   86283  158250  232722  164144  327511  653470  639351
River Rch & RM= Guadalupe River,Reach-1,1820417
   86719  158914  233567  164646  328512  655468  640554
River Rch & RM= Guadalupe River,Reach-1,1812864
   86354  158165  232385  163753  326731  651914  636619
River Rch & RM= Guadalupe River,Reach-1,1809435
   86377  158127  232250  163602  326428  651310  635579
River Rch & RM= Guadalupe River,Reach-1,1802267
   86246  157837  231774  163230  325686  649829  633848
River Rch & RM= Guadalupe River,Reach-1,1799007
   86060  157455  231169  162772  324772  648006  631822
River Rch & RM= Guadalupe River,Reach-1,1794371
   85742  156801  230136  161992  323217  644902  628387
River Rch & RM= Guadalupe River,Reach-1,1790954
   85707  156703  229960  161843  322920  644310  627618
River Rch & RM= Guadalupe River,Reach-1,1786574
   82486  151017  221765  156176  311612  621747  606676
River Rch & RM= Guadalupe River,Reach-1,1781883
   82251  150530  220995  155593  310448  619425  604094
River Rch & RM= Guadalupe River,Reach-1,1777415
   81953  149921  220034  154869  309004  616545  600916
River Rch & RM= Guadalupe River,Reach-1,1771932
   81827  149610  219499  154434  308136  614813  598773
River Rch & RM= Guadalupe River,Reach-1,1768490
   81655  149253  218930  154002  307275  613094  596852
River Rch & RM= Guadalupe River,Reach-1,1765037
   81773  149428  219149  154128  307527  613596  597122
River Rch & RM= Guadalupe River,Reach-1,1762433
   81611  149095  218623  153731  306734  612015  595369
River Rch & RM= Guadalupe River,Reach-1,1758687
   81343  148545  217755  153076  305427  609406  592484
River Rch & RM= Guadalupe River,Reach-1,1752279
   81014  147875  216702  152285  303848  606256  589027
River Rch & RM= Guadalupe River,Reach-1,1746749
   81166  148093  216964  152427  304133  606824  589252
River Rch & RM= Guadalupe River,Reach-1,1744403
   81187  148134  217026  152472  304222  607002  589434
River Rch & RM= Guadalupe River,Reach-1,1741343
   80905  147560  216126  151797  302875  604316  586494
River Rch & RM= Guadalupe River,Reach-1,1738285
   83832  152870  223898  157255  313764  626042  607520
River Rch & RM= Guadalupe River,Reach-1,1733675
   80506  146993  215425  151392  302067  602704  585818
River Rch & RM= Guadalupe River,Reach-1,1725728
   80338  146642  214868  150969  301223  601018  583933
River Rch & RM= Guadalupe River,Reach-1,1723099
   80162  146279  214293  150534  300355  599286  582009
River Rch & RM= Guadalupe River,Reach-1,1717665
   80033  146015  213878  150223  299733  598047  580649
River Rch & RM= Guadalupe River,Reach-1,1714879
   80061  145982  213747  150070  299429  597440  579590
River Rch & RM= Guadalupe River,Reach-1,1709562
   80068  145992  213758  150076  299441  597464  579598
River Rch & RM= Guadalupe River,Reach-1,1705486
   80148  146066  213797  150053  299396  597373  579113
River Rch & RM= Guadalupe River,Reach-1,1701559
   80593  146818  214844  150750  300786  600147  581497
River Rch & RM= Guadalupe River,Reach-1,1693546
   80125  145860  213333  149611  298514  595613  576497
River Rch & RM= Guadalupe River,Reach-1,1684324
   80214  145957  213413  149622  298536  595657  576186
River Rch & RM= Guadalupe River,Reach-1,1676243
   80059  145628  212884  149218  297729  594047  574367
River Rch & RM= Guadalupe River,Reach-1,1672913
   80204  145905  213304  149523  298337  595260  575620
River Rch & RM= Guadalupe River,Reach-1,1669771
   80147  145786  213116  149381  298054  594695  574994
River Rch & RM= Guadalupe River,Reach-1,1665632
   79572  144615  211275  147998  295294  589189  568955
River Rch & RM= Guadalupe River,Reach-1,1655636
   79031  143522  209569  146722  292750  584113  563439
River Rch & RM= Guadalupe River,Reach-1,1644318
   78764  142970  208693  146059  291425  581470  560503
River Rch & RM= Guadalupe River,Reach-1,1633817
   81327  147101  214260  149631  298554  595693  571466
River Rch & RM= Guadalupe River,Reach-1,1609585
   77899  141044  205529  143591  286502  571646  549076
River Rch & RM= Guadalupe River,Reach-1,1588695
   80245  144777  210508  146748  292801  584214  558437
River Rch & RM= Guadalupe River,Reach-1,1564848
   86340  155736  226481  157923  315097  628702  600971
River Rch & RM= Guadalupe River,Reach-1,1561417
   86614  156270  227297  158521  316291  631083  603467
River Rch & RM= Guadalupe River,Reach-1,1560851
     100     100     100     100     100     100     100
Boundary for River Rch & Prof#=Guadalupe River,Reach-1,1
Up Type=0
Dn Type=1
Dn Known WS=924
Boundary for River Rch & Prof#=Guadalupe River,Reach-1,2
Up Type=0
Dn Type=1
Dn Known WS=932.3
Boundary for River Rch & Prof#=Guadalupe River,Reach-1,3
Up Type=0
Dn Type=1
Dn Known WS=940
Boundary for River Rch & Prof#=Guadalupe River,Reach-1,4
Up Type=0
Dn Type=1
Dn Known WS=932.5
Boundary for River Rch & Prof#=Guadalupe River,Reach-1,5
Up Type=0
Dn Type=1
Dn Known WS=946
Boundary for River Rch & Prof#=Guadalupe River,Reach-1,6
Up Type=0
Dn Type=1
Dn Known WS=950
Boundary for River Rch & Prof#=Guadalupe River,Reach-1,7
Up Type=0
Dn Type=1
Dn Known WS=949.7

--- Guadalupe River.g01 (geometry) ---

Geom Title=Existing Conditions
Program Version=4.10

River Reach=Guadalupe River ,Reach-1
Reach XY= 30
        1756275.       13896275.      1759747.83     13912399.09
      1794577.34     13937919.42      1799785.97     13930377.28
      1826595.32     13930174.56      1852719.02       13932778.
      1858328.02     13941162.79        1912725.       13934575.
      1949035.44     13890377.01       1986809.6     13888926.48
      2020509.58     13905974.97      2022015.01     13897736.26
      2042025.01     13891732.48      2066631.05     13899966.88
      2075685.68     13871225.75      2087041.76     13873291.43
        2092475.       13886725.      2097518.27     13867984.15
       2113578.4     13877417.17      2117318.23     13867083.44
      2134309.79      13862775.5      2142018.97     13870523.36
      2156871.58     13858132.79      2170345.14     13862444.77
      2167180.47     13870177.45      2178084.68     13870985.78
      2182353.24     13882224.48      2184264.71     13871923.73
        2193075.       13877425.      2224088.89     13864951.76

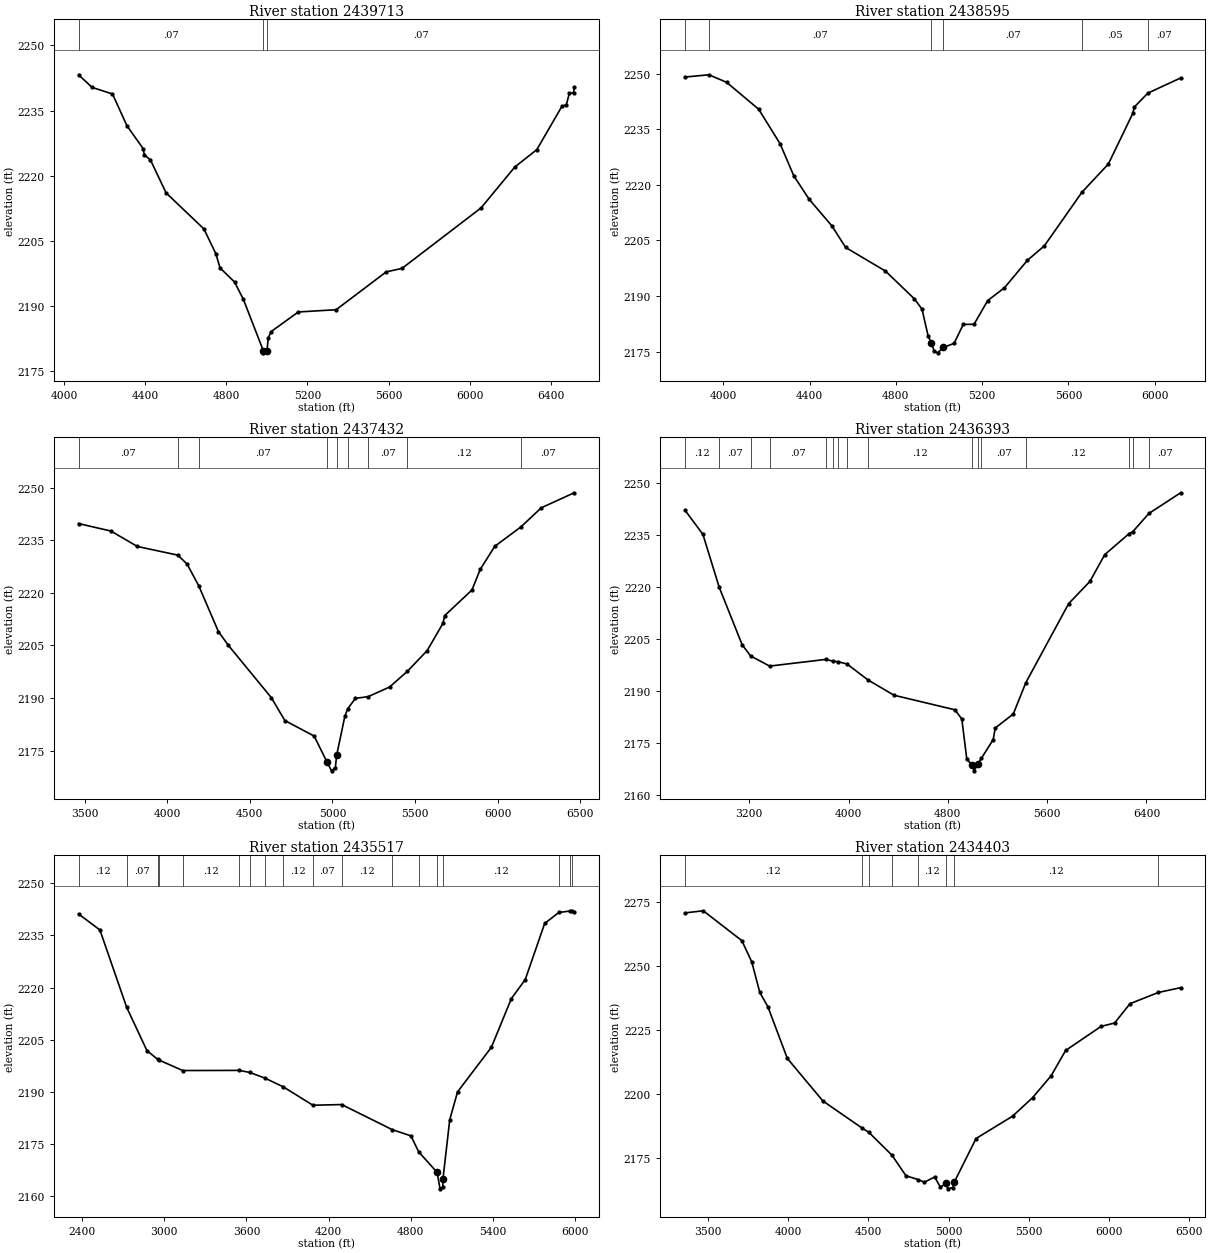
Type RM Length L Ch R = 1 ,2439713 ,1118,1118,1118
BEGIN DESCRIPTION:
Guadalupe River - 286
END DESCRIPTION:
XS GIS Cut Line= 3
        1762864.     13915667.77      1763940.61     13914896.47
      1764880.51     13914287.34
#Sta/Elev= 30
  4071.2 2243.23  4138.1 2240.33  4238.8 2238.81    4310  2231.5  4389.9 2226.23
    4396 2224.77  4425.5 2223.67    4503 2216.04  4689.6 2207.74  4748.5 2202.03
  4769.4 2198.74  4840.7 2195.52  4884.3 2191.52  4982.5 2179.71    4983 2179.21
    5001 2179.71  5006.5 2182.55  5019.6 2184.05  5155.1 2188.62  5341.8 2189.14
  5588.4 2197.84  5666.9 2198.66  6056.6 2212.59    6223    2222  6331.5    2226
  6455.5 2235.99  6476.6 2236.28  6491.7 2238.93  6512.9 2239.12  6515.6 2240.36
#Mann= 3 ,-1 , 0
  4071.2     .07       0  4982.5     .05       0    5001     .07       0
Bank Sta=4982.5,5001
XS Rating Curve= 0 ,0
Exp/Cntr=0.3,0.1

Type RM Length L Ch R = 1 ,2438595 ,1163,1163,1163
BEGIN DESCRIPTION:
Guadalupe River - 285
END DESCRIPTION:
XS GIS Cut Line= 2
      1763538.85     13916551.62      1765226.15     13914992.88
#Sta/Elev= 30
  3822.8 2249.05  3933.8 2249.66  4015.9 2247.62  4164.4 2240.36  4263.7 2231.04
  4327.2 2222.38    4398  2216.1  4504.1 2208.86  4567.6 2203.07  4751.9 2196.71
  4886.3  2189.2  4921.4 2186.42  4949.8 2179.17  4963.9 2177.42  4977.4 2175.15
  4993.6 2174.65  5020.6 2176.11  5070.1 2177.21  5112.5 2182.32  5162.4 2182.35
  5225.9 2188.76  5303.6 2192.21  5410.2 2199.64  5487.9 2203.48  5662.8 2217.99
    5785 2225.59  5898.4 2239.27  5905.2 2240.96    5968 2244.71  6119.9  2248.8
#Mann= 6 ,-1 , 0
  3822.8     .12       0  3933.8     .07       0  4963.9     .04       0
  5020.6     .07       0  5662.8     .05       0    5968     .07       0
Bank Sta=4963.9,5020.6
XS Rating Curve= 0 ,0
Exp/Cntr=0.3,0.1

Type RM Length L Ch R = 1 ,2437432 ,1039,1039,1039
BEGIN DESCRIPTION:
Guadalupe River - 284
END DESCRIPTION:
XS GIS Cut Line= 4
      1763619.19     13916728.35      1764792.28     13916776.56
      1765595.74      13916133.8      1765964.48     13915428.37
#Sta/Elev= 30
  3463.3 2239.73  3659.3  2237.6  3819.4  2233.2  4063.8 2230.73  4119.7 2228.21
  4190.1 2222.06  4309.8 2208.93  4369.9 2205.01  4630.1 2190.08  4711.6 2183.57
  4889.3 2179.13  4967.7 2171.64  4994.1 2169.22  5017.4 2170.12  5025.1 2173.64
    5075 2184.81    5092 2186.92    5139  2189.9  5214.9 2190.36  5345.2 2193.11
  5453.2  2197.6  5572.8 2203.51  5668.4 2211.27  5678.7 2213.47    5844 2220.79
  5893.8 2226.67  5982.1 2233.25    6139 2238.74  6263.5 2244.23  6462.3 2248.51
#Mann= 9 ,-1 , 0
  3463.3     .07       0  4063.8     .12       0  4190.1     .07       0
  4967.7     .04       0  5025.1     .07       0    5092     .12       0
  5214.9     .07       0  5453.2     .12       0    6139     .07       0
Bank Sta=4967.7,5025.1
XS Rating Curve= 0 ,0
Exp/Cntr=0.3,0.1

Type RM Length L Ch R = 1 ,2436393 ,876,876,876
BEGIN DESCRIPTION:
Guadalupe River - 283
END DESCRIPTION:
XS GIS Cut Line= 4
      1764920.82     13919283.37      1765531.46     13917949.61
      1765820.71     13916085.59      1766013.54     13915474.95
#Sta/Elev= 30
  2681.9 2242.26  2826.3 2235.29  2957.4 2220.03    3142 2203.42  3210.7 2200.15
    3364 2197.22  3818.7 2199.16  3877.4 2198.58  3915.7 2198.49  3987.6 2197.82
  4153.9 2193.28    4366  2188.8  4856.7 2184.59  4912.4 2181.94  4952.9 2170.25
  4993.4 2168.74  5011.8 2166.95    5044 2169.04  5069.6 2170.55  5165.4 2175.98
  5181.7 2179.32  5327.4 2183.39  5427.9 2192.41  5773.7 2215.29  5944.7 2221.69
    6064 2229.43    6261 2235.51    6291  2236.1  6419.7 2241.32  6675.5  2247.3
#Mann= 16 ,-1 , 0
  2681.9     .12       0  2957.4     .07       0  3210.7     .05       0
    3364     .07       0  3818.7     .12       0  3877.4     .07       0
  3915.7     .12       0  3987.6     .07       0  4153.9     .12       0
  4993.4     .04       0    5044     .12       0  5069.6     .07       0
  5427.9     .12       0    6261     .07       0    6291     .12       0
  6419.7     .07       0
Bank Sta=4993.4,5044
XS Rating Curve= 0 ,0
Exp/Cntr=0.3,0.1

Type RM Length L Ch R = 1 ,2435517 ,1114,1114,1114
BEGIN DESCRIPTION:
Guadalupe River - 282
END DESCRIPTION:
XS GIS Cut Line= 4
      1764969.02     13919315.54      1765627.88     13917965.68
      1766784.86     13916937.26       1767347.3     13916840.84
#Sta/Elev= 30
  2373.6 2241.19  2529.9 2236.57  2725.8 2214.26  2873.4 2201.83  2951.7 2199.33
  2963.9 2199.07  3134.9 2196.09  3546.5 2196.13  3623.4 2195.56  3734.6 2193.92
  3869.1  2191.4  4085.4  2186.1  4296.1 2186.29    4664 2179.09    4802 2177.27
  4858.9 2172.65  4993.5 2166.75  5014.5 2162.02  5034.6 2162.52  5035.8 2164.85
  5085.5 2181.95  5142.4 2189.94  5389.9 2202.81  5535.4  2216.8  5636.9 2222.29
  5778.9 2238.45  5882.3 2241.61  5963.1 2242.02    5982  2242.1  5994.3 2241.62
#Mann= 18 ,-1 , 0
  2373.6     .12       0  2725.8     .07       0  2951.7     .05       0
  2963.9     .07       0  3134.9     .12       0  3546.5     .07       0
  3623.4     .12       0  3734.6     .07       0  3869.1     .12       0
  4085.4     .07       0  4296.1     .12       0    4664     .07       0
  4858.9     .12       0  4993.5     .04       0  5035.8     .12       0
  5882.3     .07       0  5963.1     .12       0    5982     .07       0
Bank Sta=4993.5,5035.8
XS Rating Curve= 0 ,0
Exp/Cntr=0.3,0.1

Type RM Length L Ch R = 1 ,2434403 ,1008,1008,1008
BEGIN DESCRIPTION:
Guadalupe River - 281
END DESCRIPTION:
XS GIS Cut Line= 4
      1766739.76     13919598.03      1766869.96     13918447.88
       1767369.1     13917796.83       1767434.2     13916690.11
#Sta/Elev= 30
    3359 2270.57  3472.8  2271.4    3713 2259.76  3774.7  2251.5    3825 2239.56
  3875.3 2233.99  3996.1 2213.87  4217.5 2197.27  4460.6 2186.74  4503.4 2185.06
  4648.2  2176.1  4735.4 2168.07  4810.7 2166.62  4849.7 2165.59    4914 2167.62
  4949.4 2163.67  4986.4 2165.21  4994.5    2163  5027.3  2163.5  5036.5 2165.68
  5171.5 2182.62  5398.8 2191.32  5523.3 2198.52  5639.2 2207.09  5729.4 2216.94
  5949.8 2226.32  6034.2 2227.64  6130.1 2235.17  6307.6 2239.57  6445.5 2241.42
#Mann= 8 ,-1 , 0
    3359     .12       0  4460.6     .07       0  4503.4     .12       0
  4648.2     .07       0  4810.7     .12       0  4986.4     .04       0
  5036.5     .12       0  6307.6     .07       0
Bank Sta=4986.4,5036.5
XS Rating Curve= 0 ,0
Exp/Cntr=0.3,0.1

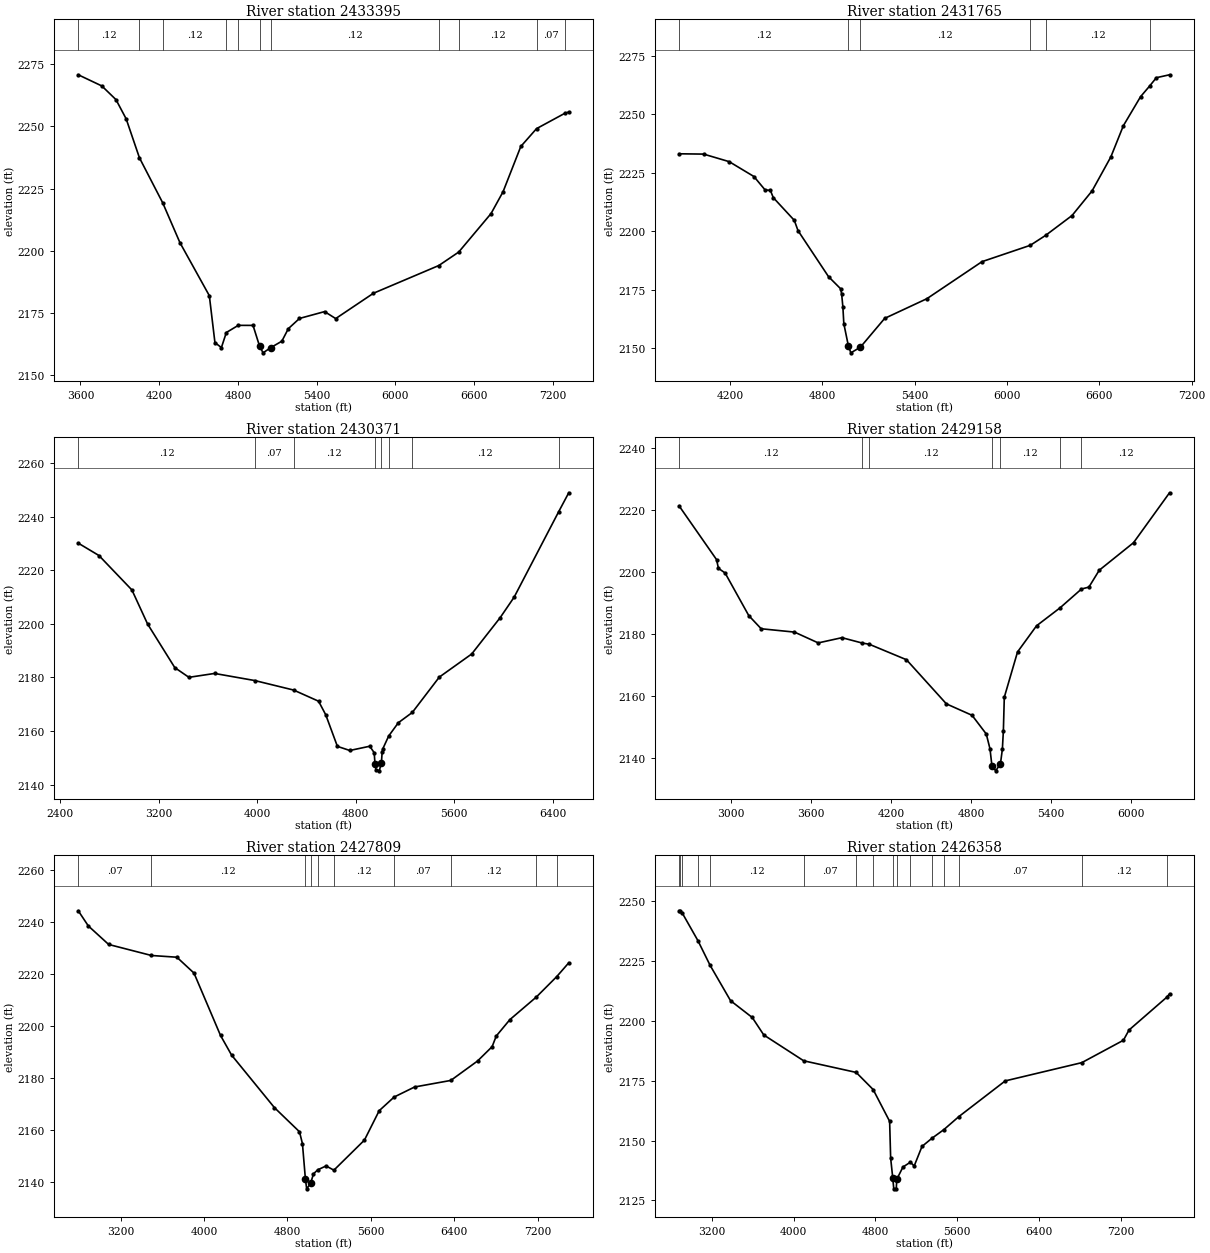
Type RM Length L Ch R = 1 ,2433395 ,1630,1630,1630
BEGIN DESCRIPTION:
Guadalupe River - 280
END DESCRIPTION:
XS GIS Cut Line= 4
       1766826.6     13919554.62      1767651.21     13918990.41
      1768475.87     13918100.65      1768757.98      13916603.3
#Sta/Elev= 30
  3583.6 2270.84  3763.1 2266.34  3870.8 2260.83  3948.6 2253.07  4049.6 2237.38
  4226.7 2219.25  4358.2 2203.17    4582 2181.81  4624.7 2162.89    4674 2160.89
  4711.5 2166.96  4802.5 2169.85  4914.9 2169.83  4964.3 2161.52  4991.3 2158.77
  5049.3 2160.85  5134.4 2163.47  5183.7 2168.51  5268.7 2172.63  5459.8 2175.39
  5544.6 2172.58  5832.2 2182.79  6329.9 2193.96  6481.4 2199.38  6727.7  2214.9
  6819.3  2223.7  6954.5 2241.95  7074.3 2249.13  7289.3  2255.3  7319.6 2255.82
#Mann= 11 ,-1 , 0
  3583.6     .12       0  4049.6     .07       0  4226.7     .12       0
  4711.5     .07       0  4802.5     .12       0  4964.3     .04       0
  5049.3     .12       0  6329.9     .07       0  6481.4     .12       0
  7074.3     .07       0  7289.3     .12       0
Bank Sta=4964.3,5049.3
XS Rating Curve= 0 ,0
Exp/Cntr=0.3,0.1

Type RM Length L Ch R = 1 ,2431765 ,1394,1394,1394
BEGIN DESCRIPTION:
Guadalupe River - 279
END DESCRIPTION:
XS GIS Cut Line= 4
      1769148.62     13919554.63      1769474.13     13918751.69
      1768692.88     13917623.22      1768866.49     13916690.06
#Sta/Elev= 30
  3867.6  2233.2  4027.3 2233.07  4193.5 2229.84  4354.3 2223.49  4426.6 2217.78
  4461.5 2217.55  4480.2 2214.46  4616.8 2204.76  4640.9 2200.36  4839.5 2180.67
  4917.7 2175.53  4924.6 2173.24  4932.6 2167.71  4938.7  2160.6  4968.4 2151.06
  4984.4 2148.13  5046.2 2150.53  5204.3 2162.86  5478.6 2171.27  5836.8  2187.1
  6150.5 2194.08  6249.9 2198.31    6422 2206.81  6552.3 2217.34  6674.3 2231.87
  6755.7 2245.21  6867.6 2257.62  6926.6 2262.18    6970 2265.72  7055.7 2266.97
#Mann= 6 ,-1 , 0
  3867.6     .12       0  4968.4     .04       0  5046.2     .12       0
  6150.5     .07       0  6249.9     .12       0  6926.6     .07       0
Bank Sta=4968.4,5046.2
XS Rating Curve= 0 ,0
Exp/Cntr=0.3,0.1

Type RM Length L Ch R = 1 ,2430371 ,1213,1213,1213
BEGIN DESCRIPTION:
Guadalupe River - 278
END DESCRIPTION:
XS GIS Cut Line= 5
       1769289.8     13919335.71      1769526.03     13918855.63
      1770570.09      13918078.3       1769846.1     13916897.06
      1769138.69     13916615.62
#Sta/Elev= 30
  2545.9 2230.15  2713.9 2225.53  2981.8 2212.66    3109 2199.95    3330 2183.66
  3444.7 2180.04  3653.2 2181.49  3979.3 2178.84  4294.9 2175.29  4497.7 2171.12
  4555.8 2166.06  4650.5 2154.26  4751.2 2152.72  4913.5 2154.31  4949.5 2151.87
  4956.1  2147.6  4963.6 2145.62  4990.6 2145.12  5008.1 2148.13  5014.1 2152.24
    5020 2153.41  5067.1 2158.13  5145.6 2163.09    5259 2166.93  5478.3 2180.13
  5741.3 2188.76  5972.4 2202.32  6085.7 2209.96  6446.6  2241.8  6529.4 2248.96
#Mann= 8 ,-1 , 0
  2545.9     .12       0  3979.3     .07       0  4294.9     .12       0
  4956.1     .04       0  5008.1     .12       0  5067.1     .07       0
    5259     .12       0  6446.6     .07       0
Bank Sta=4956.1,5008.1
XS Rating Curve= 0 ,0
Exp/Cntr=0.3,0.1

Type RM Length L Ch R = 1 ,2429158 ,1349,1349,1349
BEGIN DESCRIPTION:
Guadalupe River - 277
END DESCRIPTION:
XS GIS Cut Line= 2
      1769430.74     13919185.71      1772295.34     13916885.36
#Sta/Elev= 30
  2613.4 2221.32  2894.3 2203.95  2908.7 2201.12  2958.3 2199.63  3135.9 2185.85
  3228.7 2181.61  3478.2 2180.53    3656 2177.04  3833.6 2178.73  3984.2 2177.01
    4038 2176.61  4316.8 2171.61    4616 2157.35  4808.1 2153.66  4914.6 2147.63
  4942.5 2142.84  4956.9 2137.41  4985.6 2135.72  5020.9 2138.02  5035.3 2142.72
  5042.8 2148.66  5049.7 2159.49  5148.9 2174.13  5291.3 2182.57  5466.5 2188.34
  5627.8 2194.45  5683.3 2195.06    5761 2200.52  6017.5  2209.4  6287.3 2225.53
#Mann= 7 ,-1 , 0
  2613.4     .12       0  3984.2     .07       0    4038     .12       0
  4956.9     .04       0  5020.9     .12       0  5466.5     .07       0
  5627.8     .12       0
Bank Sta=4956.9,5020.9
XS Rating Curve= 0 ,0
Exp/Cntr=0.3,0.1

Type RM Length L Ch R = 1 ,2427809 ,1451,1451,1451
BEGIN DESCRIPTION:
Guadalupe River - 276
END DESCRIPTION:
XS GIS Cut Line= 4
      1770689.41     13920704.84      1770797.92     13919706.56
      1772425.52     13918165.76      1772512.33     13916711.75
#Sta/Elev= 30
    2795 2244.35  2891.7 2238.51  3086.5 2231.39  3496.5 2227.15  3740.4 2226.48
  3904.5 2220.38  4158.9 2196.37  4264.9 2188.82  4675.5 2168.61  4915.8 2159.32
  4944.1 2154.76  4972.4  2141.2  4984.7 2137.36  5021.8 2139.42  5050.1 2143.14
  5090.9 2144.68  5170.7 2146.17  5245.6 2144.54  5538.4 2156.11    5680 2167.43
  5823.4 2172.69  6019.4 2176.55  6366.3 2179.07  6623.1 2186.56  6762.4 2192.06
  6802.5 2196.18  6932.7 2202.47  7185.7 2211.14  7381.2 2218.99    7497 2224.32
#Mann= 10 ,-1 , 0
    2795     .07       0  3496.5     .12       0  4972.4     .04       0
  5021.8     .12       0  5090.9     .07       0  5245.6     .12       0
  5823.4     .07       0  6366.3     .12       0  7185.7     .07       0
  7381.2     .12       0
Bank Sta=4972.4,5021.8
XS Rating Curve= 0 ,0
Exp/Cntr=0.3,0.1

Type RM Length L Ch R = 1 ,2426358 ,2683,2683,2683
BEGIN DESCRIPTION:
Guadalupe River - 275
END DESCRIPTION:
XS GIS Cut Line= 3
      1771904.67     13921225.68      1772881.25     13920118.88
      1772729.37      13916799.3
#Sta/Elev= 30
  2879.3 2246.11  2885.3 2246.04  2909.3 2245.28  3064.1 2233.62  3183.1 2223.31
  3383.2 2208.53  3595.7 2201.49  3708.6 2194.18  4098.9 2183.39  4612.2 2178.53
  4778.3 2171.38  4939.8 2158.09  4949.8 2142.68  4969.9 2134.59  4980.4 2129.85
  5004.6 2129.85  5009.9 2133.84    5070 2138.97  5142.7 2140.98  5180.1 2139.41
  5256.5 2147.58  5351.5 2150.92  5469.8 2154.59  5616.9 2160.05    6071 2174.98
    6820 2182.61  7227.1 2191.97  7282.3 2196.26  7651.1 2209.96  7678.4 2211.38
#Mann= 16 ,-1 , 0
  2879.3     .12       0  2885.3     .07       0  2909.3     .12       0
  3064.1     .07       0  3183.1     .12       0  4098.9     .07       0
  4612.2     .12       0  4778.3     .07       0  4969.9     .04       0
  5009.9     .07       0  5142.7     .12       0  5351.5     .07       0
  5469.8     .12       0  5616.9     .07       0    6820     .12       0
  7651.1     .07       0
Bank Sta=4969.9,5009.9
XS Rating Curve= 0 ,0
Exp/Cntr=0.3,0.1

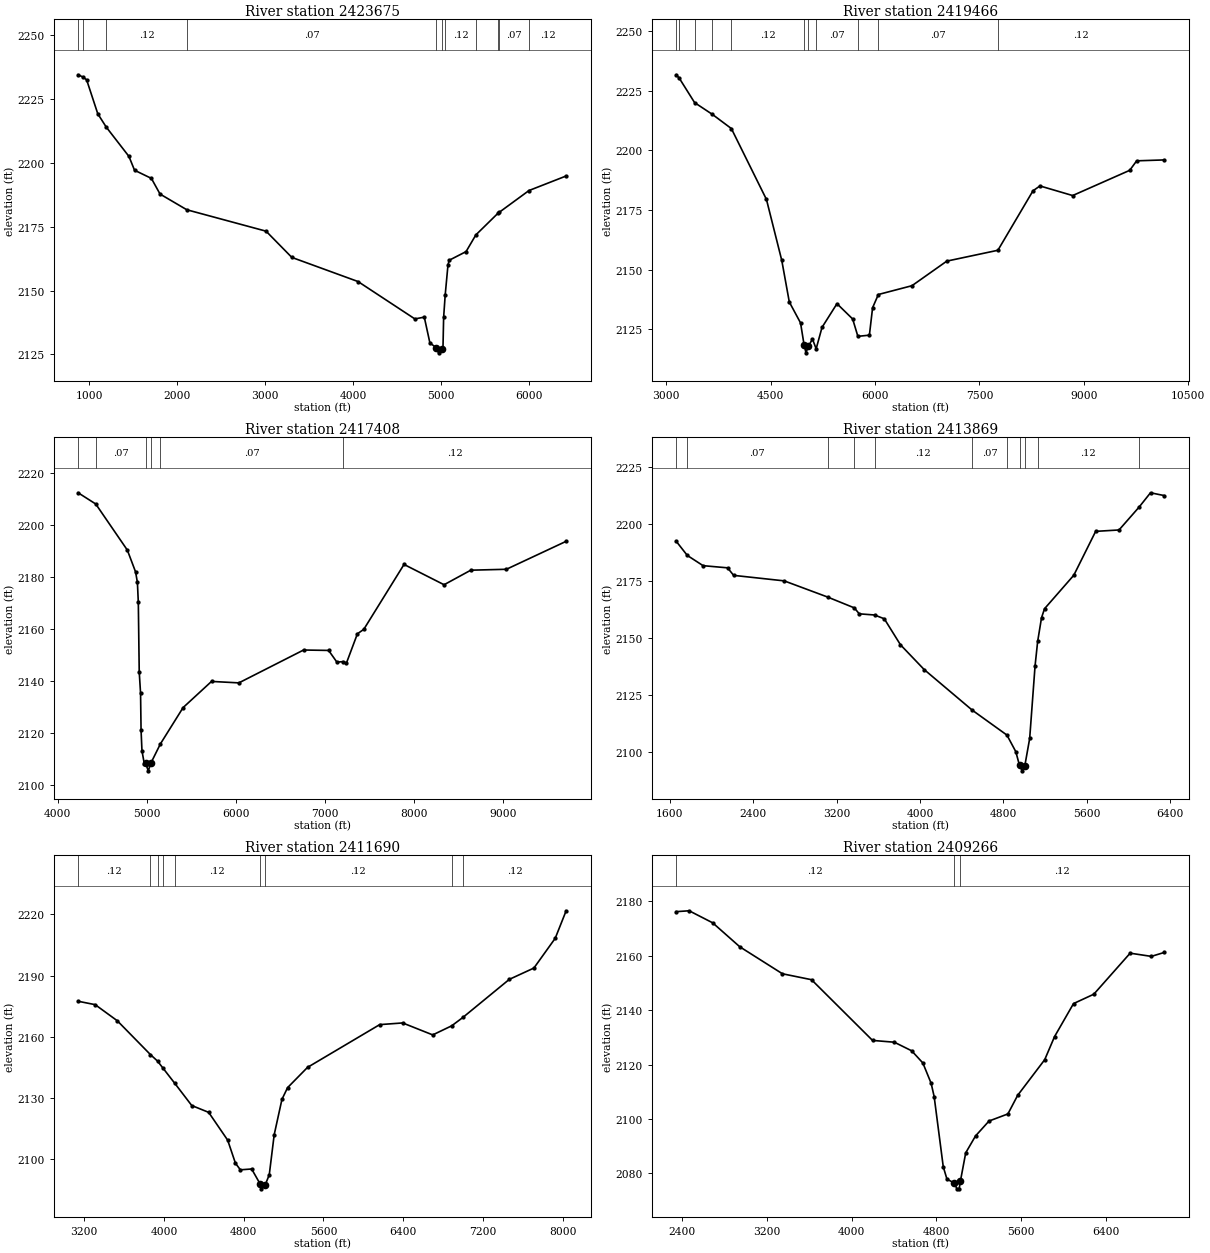
Type RM Length L Ch R = 1 ,2423675 ,4209,4209,4209
BEGIN DESCRIPTION:
Guadalupe River - 274
END DESCRIPTION:
XS GIS Cut Line= 4
      1772013.16     13921269.09      1773293.58     13919836.76
      1774530.55     13919619.75      1776049.66     13917796.82
#Sta/Elev= 30
   871.9 2234.55   923.6 2233.72   968.4 2232.59  1095.5 2219.26  1191.2 2214.08
  1449.9 2202.57  1513.4 2197.16  1704.9 2193.97  1803.5 2187.83  2107.8 2181.68
  3009.3 2173.29  3302.2 2163.02  4055.3 2153.56  4701.8 2138.92  4808.6 2139.63
  4872.4 2129.52  4942.7 2127.72  4970.3 2125.64  5006.4 2127.15  5020.8 2126.95
  5028.6 2139.54  5046.5 2148.34    5078 2160.05  5092.3 2161.91  5283.7 2165.29
  5394.9 2171.82  5646.2  2180.3    5658 2180.61  5999.8 2189.22  6421.9 2194.91
#Mann= 11 ,-1 , 0
   871.9     .12       0   923.6     .07       0  1191.2     .12       0
  2107.8     .07       0  4942.7     .04       0  5006.4     .07       0
  5046.5     .12       0  5394.9     .07       0  5646.2     .12       0
    5658     .07       0  5999.8     .12       0
Bank Sta=4942.7,5006.4
XS Rating Curve= 0 ,0
Exp/Cntr=0.3,0.1

Type RM Length L Ch R = 1 ,2419466 ,2058,2058,2058
BEGIN DESCRIPTION:
Guadalupe River - 273
END DESCRIPTION:
XS GIS Cut Line= 4
      1772034.92     13921898.39      1775159.89     13921464.37
      1776223.26     13919988.67      1776201.57     13917949.37
#Sta/Elev= 30
  3141.5 2231.68  3186.2 2230.23  3406.3    2220  3661.8 2215.07  3934.4 2209.13
  4438.6 2179.41  4658.7 2153.85    4767 2136.41  4928.6 2127.64    4979  2118.5
  5006.6 2115.09  5039.6 2117.84  5100.2 2120.85  5152.9 2116.78  5237.2 2125.77
  5452.2  2135.7  5677.4 2129.29  5752.4 2122.01    5918  2122.5  5964.1 2134.02
  6046.8 2139.55  6529.9 2143.24  7030.6 2153.55  7764.8  2158.1  8269.1 2183.03
  8369.1 2185.07  8839.1 2181.04  9659.1 2191.62  9759.1  2195.6 10154.8 2195.98
#Mann= 11 ,-1 , 0
  3141.5     .12       0  3186.2     .07       0  3406.3     .12       0
  3661.8     .07       0  3934.4     .12       0    4979     .04       0
  5039.6     .12       0  5152.9     .07       0  5752.4     .12       0
  6046.8     .07       0  7764.8     .12       0
Bank Sta=4979,5039.6
XS Rating Curve= 0 ,0
Exp/Cntr=0.3,0.1

Type RM Length L Ch R = 1 ,2417408 ,3539,3539,3539
BEGIN DESCRIPTION:
Guadalupe River - 272
END DESCRIPTION:
XS GIS Cut Line= 4
      1775659.02     13923113.65       1775290.1     13921529.47
      1776396.87     13919901.87      1776353.47     13918013.89
#Sta/Elev= 30
  4229.1 2212.47  4427.1 2208.15  4782.2  2190.4  4874.6 2182.01  4895.1 2177.98
  4905.4 2170.27  4915.6 2143.51  4930.6 2135.32  4936.2 2121.05  4946.4 2113.16
  4973.2 2108.08  4987.5  2108.4  5016.9 2105.46  5049.1 2108.62  5153.4 2115.82
  5408.5  2129.8  5727.9 2139.87  6034.9 2139.31  6762.2 2151.96  7043.6  2151.8
  7136.4  2147.3    7206 2147.49  7244.2 2146.97  7366.9  2158.2  7438.7 2159.91
  7890.8 2184.89  8340.9 2177.08    8641 2182.68  9041.1 2183.03  9712.4 2193.79
#Mann= 6 ,-1 , 0
  4229.1     .12       0  4427.1     .07       0  4987.5     .04       0
  5049.1     .12       0  5153.4     .07       0    7206     .12       0
Bank Sta=4987.5,5049.1
XS Rating Curve= 0 ,0
Exp/Cntr=0.3,0.1

Type RM Length L Ch R = 1 ,2413869 ,2179,2179,2179
BEGIN DESCRIPTION:
Guadalupe River - 271
END DESCRIPTION:
XS GIS Cut Line= 3
      1776223.23     13922874.98      1777503.64      13921898.4
      1778263.19     13918925.32
#Sta/Elev= 30
  1662.4 2192.51  1768.9  2186.3  1920.2 2181.81  2155.1 2180.86  2213.2 2177.56
  2697.6 2175.15  3113.5 2168.07  3370.2 2163.31  3417.6  2160.7    3564 2160.19
  3657.5 2158.53  3812.9 2147.12    4040 2136.27  4501.3 2118.46  4833.4 2107.55
  4918.4 2100.29  4954.1 2094.23  4979.1 2091.88    5004 2093.87  5051.5 2106.08
  5103.1 2137.88  5127.9 2148.58    5165 2158.97    5194 2162.94  5474.7 2177.63
  5684.1 2196.85  5908.1 2197.46  6100.1 2207.46  6209.9 2213.76  6341.3 2212.54
#Mann= 11 ,-1 , 0
  1662.4     .12       0  1768.9     .07       0  3113.5     .12       0
  3370.2     .07       0    3564     .12       0  4501.3     .07       0
  4833.4     .12       0  4954.1     .04       0    5004     .12       0
  5127.9     .12       0  6100.1     .07       0
Bank Sta=4954.1,5004
XS Rating Curve= 0 ,0
Exp/Cntr=0.3,0.1

Type RM Length L Ch R = 1 ,2411690 ,2424,2424,2424
BEGIN DESCRIPTION:
Guadalupe River - 270
END DESCRIPTION:
XS GIS Cut Line= 4
       1778284.9     13923005.17      1778979.34     13922115.41
      1779738.89     13921334.16      1778480.57      13918969.4
#Sta/Elev= 30
  3138.8  2177.4  3309.9 2175.73  3531.5 2167.85  3863.5  2151.3  3935.6 2148.08
  3986.7 2144.85  4108.3  2137.2  4278.9  2126.3  4448.7 2122.95  4639.5 2109.32
  4717.2 2098.04  4766.8 2094.79    4880  2095.2  4964.9 2087.88  4977.2 2085.47
  5014.3 2087.21  5056.7 2092.35  5106.2 2111.99  5184.1 2129.34  5240.7 2135.07
  5440.5 2144.99  6164.9 2165.95  6395.2 2166.77  6697.2 2160.91  6887.5 2165.37
  6999.8 2169.47  7465.5 2188.13  7712.2 2193.67  7926.2 2208.26  8035.8 2221.74
#Mann= 9 ,-1 , 0
  3138.8     .12       0  3863.5     .07       0  3935.6     .12       0
  3986.7     .07       0  4108.3     .12       0  4964.9     .04       0
  5014.3     .12       0  6887.5     .07       0  6999.8     .12       0
Bank Sta=4964.9,5014.3
XS Rating Curve= 0 ,0
Exp/Cntr=0.3,0.1

Type RM Length L Ch R = 1 ,2409266 ,2929,2929,2929
BEGIN DESCRIPTION:
Guadalupe River - 269
END DESCRIPTION:
XS GIS Cut Line= 4
      1778588.75      13923330.7      1780238.02     13924046.83
       1781540.1     13922961.76      1782212.83     13922072.03
#Sta/Elev= 30
  2342.9 2176.25  2465.4 2176.57  2687.4 2172.14  2943.8 2163.31  3346.3 2153.39
  3620.7 2151.21    4197 2128.87  4402.7 2128.21  4566.6 2125.05  4672.1 2120.57
  4750.3 2113.11  4778.9  2108.2  4864.8 2082.39  4899.9 2077.81  4970.2 2076.39
  4993.3 2074.26  5014.9 2074.26  5027.5 2077.25    5077 2087.51  5169.4 2093.71
    5297 2099.21  5475.3 2101.82  5567.7 2108.68  5822.9 2121.78  5915.9 2130.28
  6094.9 2142.42  6286.4 2145.87  6629.7 2160.97  6829.5 2159.79  6951.3 2161.23
#Mann= 3 ,-1 , 0
  2342.9     .12       0  4970.2     .04       0  5027.5     .12       0
Bank Sta=4970.2,5027.5
XS Rating Curve= 0 ,0
Exp/Cntr=0.3,0.1