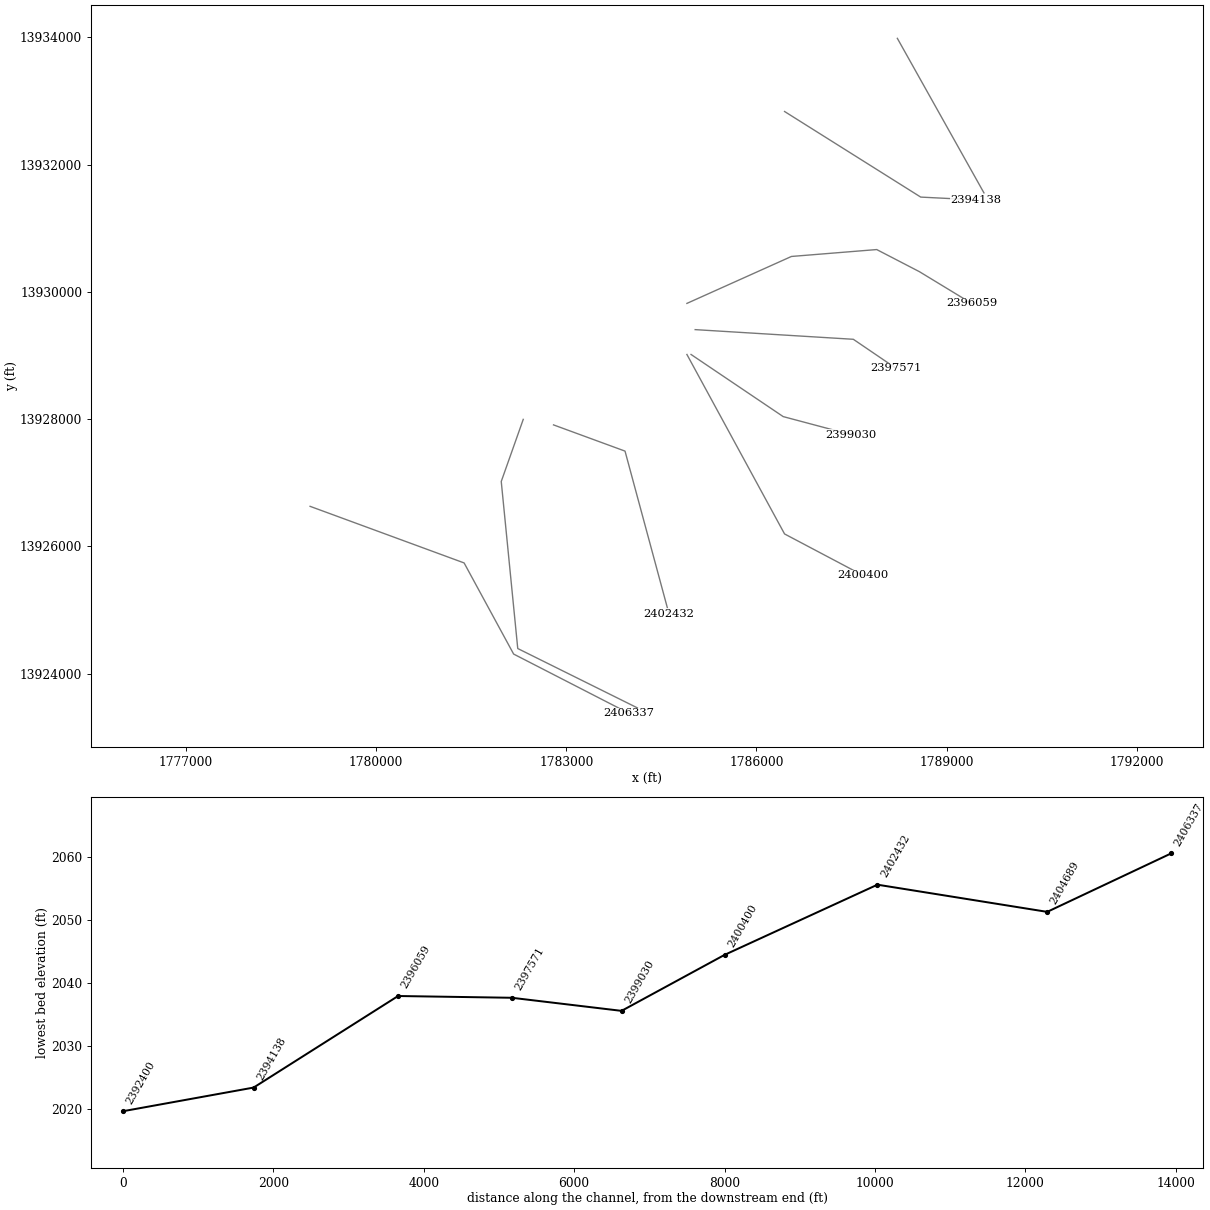
HEC-RAS study Guadalupe River.prj: Guadalupe River Base Level Engineering

--- Guadalupe River.g01 (geometry) --- (continued)

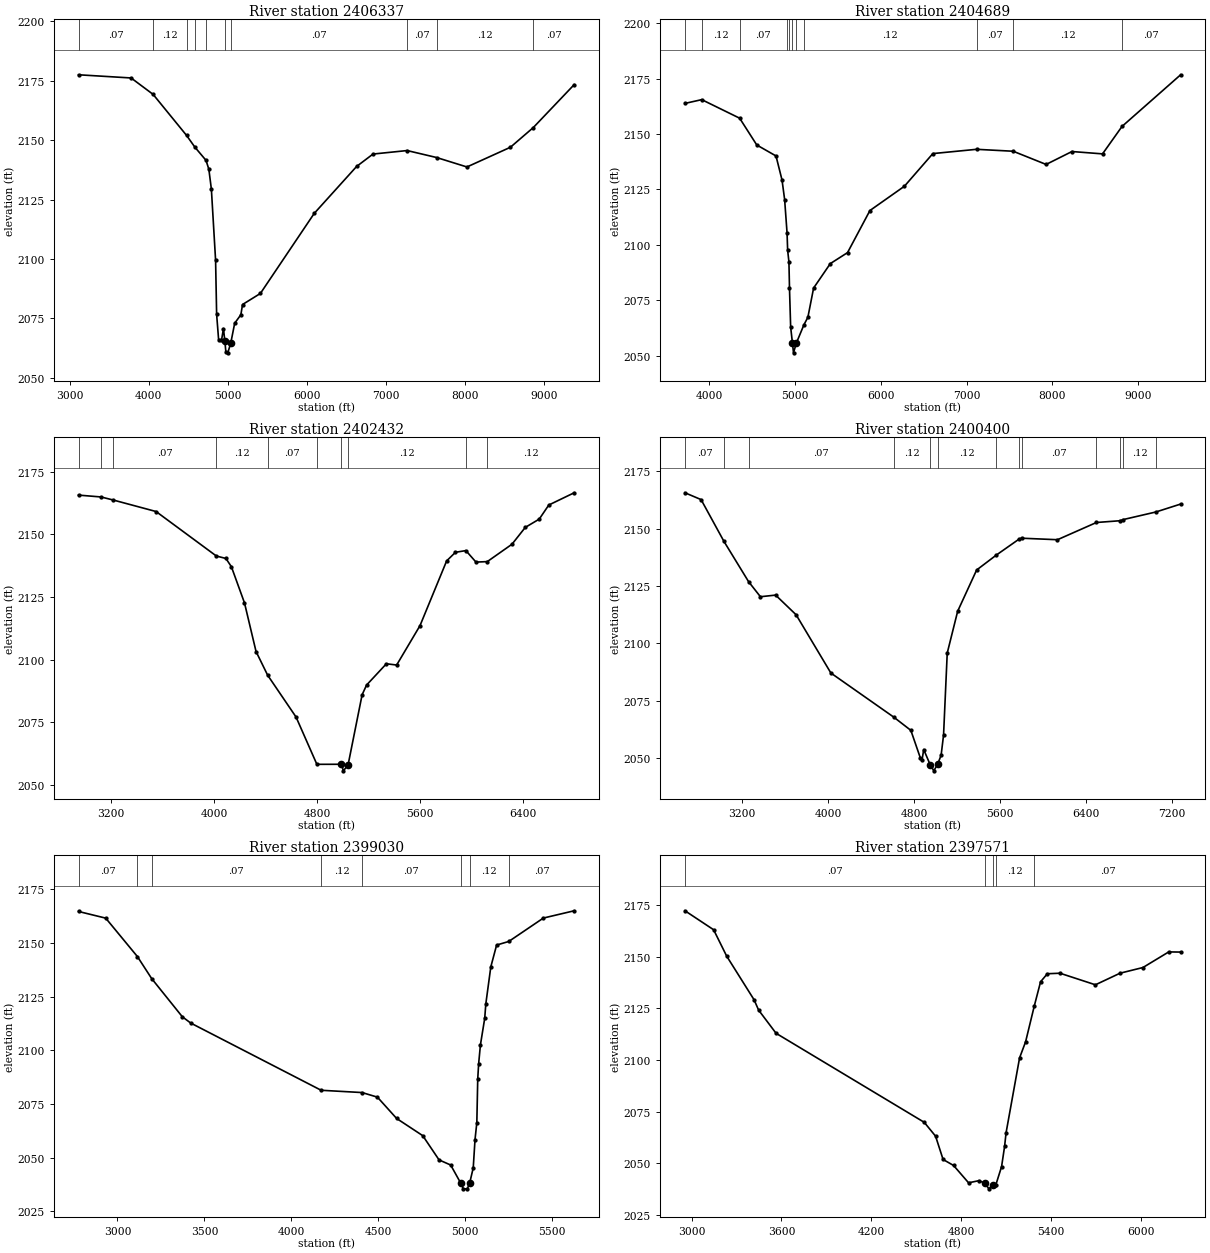
Type RM Length L Ch R = 1 ,2406337 ,1648,1648,1648
BEGIN DESCRIPTION:
Guadalupe River - 268
END DESCRIPTION:
XS GIS Cut Line= 4
       1778957.6     13926629.31      1781388.19     13925739.54
      1782169.44     13924307.25      1783991.18     13923374.69
#Sta/Elev= 30
  3113.7 2177.45  3778.6 2176.11  4057.1  2169.2  4479.2 2151.98  4584.4 2147.04
  4725.6 2141.47  4761.5 2137.75  4793.5 2129.35  4846.7  2099.5  4859.9 2076.72
  4885.1 2066.02  4921.3 2065.74  4946.1 2070.76  4963.9 2065.44  4976.3 2061.04
  5000.8 2060.54  5038.4  2064.6  5088.1 2072.99  5166.2 2076.55  5187.5 2080.86
  5413.1 2085.51  6094.5  2119.2  6630.1 2138.92  6837.1 2144.12  7268.4 2145.59
  7639.9 2142.67  8024.6 2138.69  8574.2 2146.98  8863.8 2155.27  9380.1  2173.3
#Mann= 10 ,-1 , 0
  3113.7     .07       0  4057.1     .12       0  4479.2     .07       0
  4584.4     .12       0  4725.6     .07       0  4963.9     .04       0
  5038.4     .07       0  7268.4     .07       0  7639.9     .12       0
  8863.8     .07       0
Bank Sta=4963.9,5038.4
XS Rating Curve= 0 ,0
Exp/Cntr=0.3,0.1

Type RM Length L Ch R = 1 ,2404689 ,2257,2257,2257
BEGIN DESCRIPTION:
Guadalupe River - 267
END DESCRIPTION:
XS GIS Cut Line= 4
      1782321.34     13927996.46      1781974.13     13927019.92
      1782234.55     13924394.06       1784121.3     13923461.52
#Sta/Elev= 30
    3717 2163.83  3912.3 2165.53  4354.5 2157.15  4554.3 2145.06  4778.5 2140.11
  4848.8 2129.23    4879 2120.45  4907.2 2105.43  4914.2 2097.56  4929.2 2092.26
  4935.8 2080.33  4949.3 2062.86  4969.4 2055.91  4982.5 2051.25  5015.1 2055.61
  5104.3 2063.92  5150.3 2067.32  5216.9  2080.5  5411.6 2091.52  5612.5 2096.48
  5873.8 2115.48  6275.8 2126.44  6607.4 2141.18  7117.2 2143.11    7544 2142.24
  7928.1 2136.28  8229.3 2142.11  8586.2 2141.05  8813.4 2153.44  9496.8 2176.75
#Mann= 11 ,-1 , 0
    3717     .07       0  3912.3     .12       0  4354.5     .07       0
  4907.2     .12       0  4935.8     .07       0  4969.4     .04       0
  5015.1     .07       0  5104.3     .12       0  7117.2     .07       0
    7544     .12       0  8813.4     .07       0
Bank Sta=4969.4,5015.1
XS Rating Curve= 0 ,0
Exp/Cntr=0.3,0.1

Type RM Length L Ch R = 1 ,2402432 ,2032,2032,2032
BEGIN DESCRIPTION:
Guadalupe River - 266
END DESCRIPTION:
XS GIS Cut Line= 3
      1782798.77     13927909.69      1783927.26     13927497.35
      1784621.23     13924938.34
#Sta/Elev= 30
  2946.3  2165.6  3121.5 2164.86  3216.9 2163.63  3549.1 2159.05    4018 2141.29
  4092.1 2140.32  4134.7 2137.02  4236.5 2122.59  4326.3 2103.19  4416.5 2093.73
  4637.2 2077.05  4799.2 2058.17  4989.5 2058.19  5005.1 2055.57  5041.7 2057.92
  5150.8 2085.92  5185.5  2089.8  5339.6  2098.3  5419.3 2097.79  5600.8 2113.51
    5808 2139.35  5876.4 2142.78  5957.5 2143.46  6035.9 2138.87  6123.8 2139.06
  6315.7 2145.99  6419.3 2152.72  6527.6 2156.02  6602.1 2161.65  6799.2 2166.53
#Mann= 10 ,-1 , 0
  2946.3     .07       0  3121.5     .12       0  3216.9     .07       0
    4018     .12       0  4416.5     .07       0  4799.2     .12       0
  4989.5     .04       0  5041.7     .12       0  5957.5     .07       0
  6123.8     .12       0
Bank Sta=4989.5,5041.7
XS Rating Curve= 0 ,0
Exp/Cntr=0.3,0.1

Type RM Length L Ch R = 1 ,2400400 ,1370,1370,1370
BEGIN DESCRIPTION:
Guadalupe River - 265
END DESCRIPTION:
XS GIS Cut Line= 3
      1784903.82     13929016.45      1786444.62     13926195.27
      1787680.83     13925544.63
#Sta/Elev= 30
  2669.2 2165.62    2819 2162.65  3032.1 2144.41  3261.2 2126.86  3371.1 2120.31
  3512.5 2121.02  3703.2 2112.44  4026.8 2087.05  4611.4 2067.84  4770.7 2062.06
  4858.5 2050.12  4874.2 2048.96  4890.3  2053.7  4949.7 2047.18  4984.7 2044.42
  5021.2 2047.46  5052.3 2051.21    5075 2060.02  5109.2 2095.76  5206.3    2114
  5382.7 2131.96  5566.5 2138.49  5780.4 2145.52  5801.3 2145.82  6134.8 2145.16
  6497.5 2152.67  6718.1 2153.44  6745.4 2153.93  7050.6 2157.25  7280.7  2160.7
#Mann= 13 ,-1 , 0
  2669.2     .07       0  3032.1     .12       0  3261.2     .07       0
  4611.4     .12       0  4949.7     .04       0  5021.2     .12       0
  5566.5     .07       0  5780.4     .12       0  5801.3     .07       0
  6497.5     .12       0  6718.1     .07       0  6745.4     .12       0
  7050.6     .07       0
Bank Sta=4949.7,5021.2
XS Rating Curve= 0 ,0
Exp/Cntr=0.3,0.1

Type RM Length L Ch R = 1 ,2399030 ,1459,1459,1459
BEGIN DESCRIPTION:
Guadalupe River - 264
END DESCRIPTION:
XS GIS Cut Line= 3
      1784968.92     13929016.45      1786422.92     13928039.89
      1787486.32     13927757.76
#Sta/Elev= 30
  2775.8 2164.75  2932.3 2161.64  3114.8 2143.72  3196.8 2133.47  3373.3 2115.67
  3421.6 2112.75  4171.9 2081.44  4407.4 2080.38  4495.5 2078.24    4606 2068.31
  4756.4 2060.29  4850.2    2049  4917.1 2046.61  4974.3 2038.26  4990.2 2035.52
  5012.6 2035.52  5026.1 2038.14  5046.8 2045.29  5057.1  2058.5  5067.5 2066.39
  5072.7 2086.74  5077.9 2093.76  5088.1 2102.55  5112.9 2114.99  5119.2  2121.7
  5147.9 2138.94  5181.3  2149.1  5251.1 2150.77  5450.3 2161.68  5627.5 2165.07
#Mann= 8 ,-1 , 0
  2775.8     .07       0  3114.8     .12       0  3196.8     .07       0
  4171.9     .12       0  4407.4     .07       0  4974.3     .04       0
  5026.1     .12       0  5251.1     .07       0
Bank Sta=4974.3,5026.1
XS Rating Curve= 0 ,0
Exp/Cntr=0.3,0.1

Type RM Length L Ch R = 1 ,2397571 ,1512,1512,1512
BEGIN DESCRIPTION:
Guadalupe River - 263
END DESCRIPTION:
XS GIS Cut Line= 3
      1785034.05     13929407.08      1787529.69     13929255.17
      1788200.84     13928800.52
#Sta/Elev= 30
  2955.8 2172.17  3147.1 2162.99  3234.5  2150.2  3417.6 2129.07  3447.7  2124.1
  3564.4 2112.87  4554.1 2069.79  4629.8 2063.08  4679.9 2051.81  4750.1  2048.9
  4850.2 2040.52  4920.4 2041.57  4960.5 2040.27  4985.8  2037.6  5010.5 2039.38
    5033 2039.69  5070.7 2048.37  5090.7  2058.1  5100.7 2064.75  5190.9    2101
    5231 2108.74  5289.6 2126.22  5331.1  2137.8  5376.4  2141.7  5460.8 2141.95
  5697.5 2136.35  5862.3 2141.97    6015 2144.71  6187.2 2152.26  6266.7 2152.19
#Mann= 5 ,-1 , 0
  2955.8     .07       0  4960.5     .04       0  5010.5     .07       0
    5033     .12       0  5289.6     .07       0
Bank Sta=4960.5,5010.5
XS Rating Curve= 0 ,0
Exp/Cntr=0.3,0.1

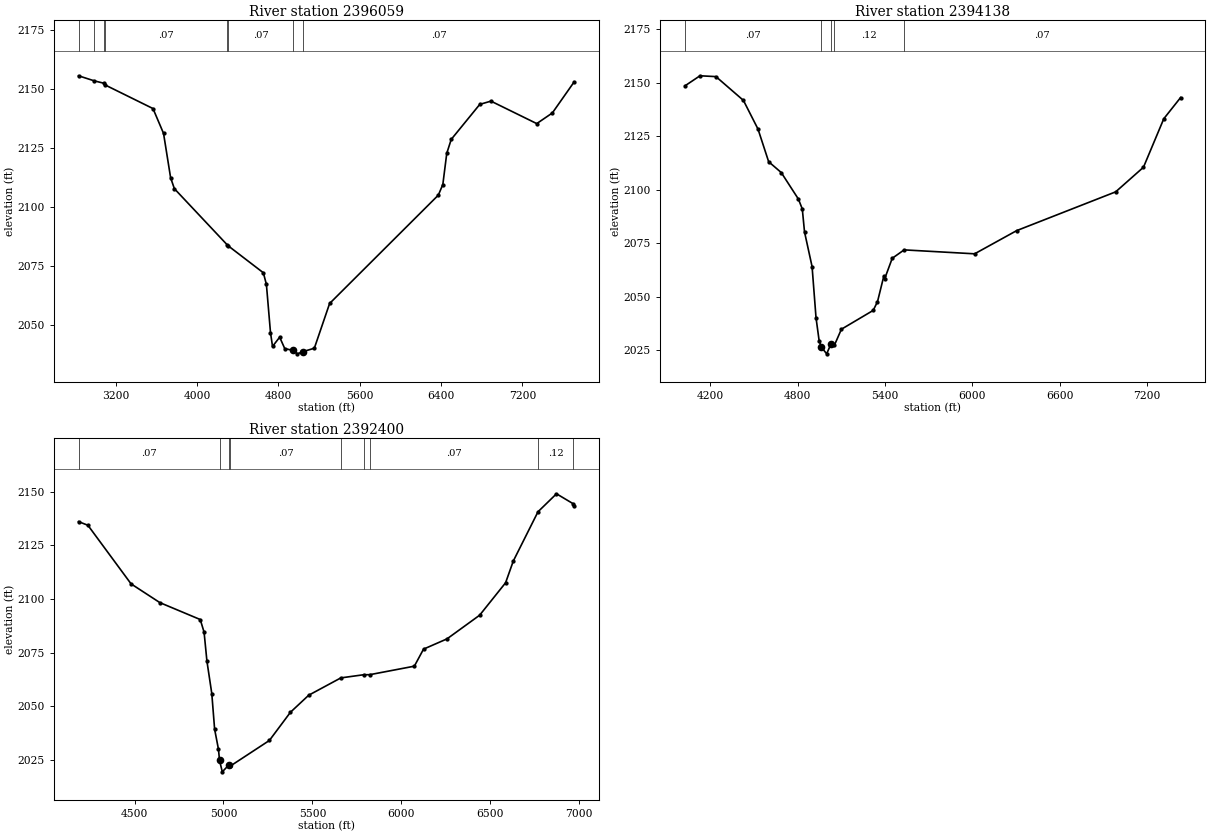
Type RM Length L Ch R = 1 ,2396059 ,1921,1921,1921
BEGIN DESCRIPTION:
Guadalupe River - 262
END DESCRIPTION:
XS GIS Cut Line= 5
      1784903.83     13929819.41      1786553.12     13930557.25
      1787898.61     13930665.76      1788571.35     13930318.53
      1789395.51      13929819.7
#Sta/Elev= 30
  2832.4 2155.45  2989.2 2153.28  3078.9 2152.33  3095.7 2151.54  3565.3 2141.59
  3669.1 2131.08  3738.7 2112.33  3775.8  2107.7  4295.3 2083.98  4303.7  2083.6
  4651.1 2072.16  4681.2 2067.24  4721.4 2046.87  4741.4 2041.01  4811.7 2044.92
  4861.8 2040.09  4942.1 2039.35  4986.6 2037.88    5042 2038.83  5152.8 2040.25
  5303.2 2059.17  6372.8 2104.98  6417.1 2109.45  6455.8 2122.65  6500.1 2128.57
  6780.8 2143.36  6890.7 2144.73  7341.3 2135.23  7494.6 2139.72  7709.5 2152.87
#Mann= 8 ,-1 , 0
  2832.4     .12       0  2989.2     .07       0  3078.9     .12       0
  3095.7     .07       0  4295.3     .12       0  4303.7     .07       0
  4942.1     .04       0    5042     .07       0
Bank Sta=4942.1,5042
XS Rating Curve= 0 ,0
Exp/Cntr=0.3,0.1

Type RM Length L Ch R = 1 ,2394138 ,1738,1738,1738
BEGIN DESCRIPTION:
Guadalupe River - 261
END DESCRIPTION:
XS GIS Cut Line= 3
      1786444.58     13932835.92      1788593.05     13931490.41
      1789460.55     13931447.04
#Sta/Elev= 30
  4026.9 2148.54    4130 2153.24  4239.6 2152.85  4428.2 2141.74  4528.4 2128.33
  4601.5 2113.09  4688.1 2108.02  4805.4 2095.68  4832.5 2091.03  4847.8 2080.28
  4899.7 2064.08  4926.8 2040.17    4948 2029.54  4963.3 2026.49  4999.8 2023.33
  5030.3  2028.1    5053 2027.36  5101.1 2034.83  5319.3 2043.62  5348.9 2047.68
  5392.4 2059.68  5398.3 2058.42  5450.1 2067.97  5531.8  2071.9  6015.9 2070.06
  6304.7  2080.9  6984.4 2099.01  7175.3 2110.51  7314.8 2133.16  7430.5 2143.09
#Mann= 5 ,-1 , 0
  4026.9     .07       0  4963.3     .04       0  5030.3     .07       0
    5053     .12       0  5531.8     .07       0
Bank Sta=4963.3,5030.3
XS Rating Curve= 0 ,0
Exp/Cntr=0.3,0.1

Type RM Length L Ch R = 1 ,2392400 ,1742,1742,1742
BEGIN DESCRIPTION:
Guadalupe River - 260
END DESCRIPTION:
XS GIS Cut Line= 2
      1788224.15     13933986.04      1789590.65      13931556.7
#Sta/Elev= 30
  4184.8 2135.99  4237.6 2134.29  4480.4 2107.02  4642.3  2098.3  4869.3 2090.43
  4890.9 2084.58  4906.9 2071.11  4934.3 2055.99  4950.2 2039.39  4971.9 2030.06
  4977.7 2024.94  4993.3 2019.57  5031.2 2022.86  5036.9 2022.17  5258.1 2034.16
  5376.6 2047.29  5479.3 2055.22  5660.1 2063.28    5788 2064.74  5822.4 2064.77
  6073.3 2068.73    6125 2076.66  6256.9 2081.43  6440.5 2092.44  6586.5 2107.54
  6629.8 2117.65  6768.7 2140.57  6872.7 2148.94  6966.3 2144.32  6972.1 2143.46
#Mann= 9 ,-1 , 0
  4184.8     .07       0  4977.7     .04       0  5031.2     .12       0
  5036.9     .07       0  5660.1     .07       0    5788     .05       0
  5822.4     .07       0  6768.7     .12       0  6966.3     .07       0
Bank Sta=4977.7,5031.2
XS Rating Curve= 0 ,0
Exp/Cntr=0.3,0.1