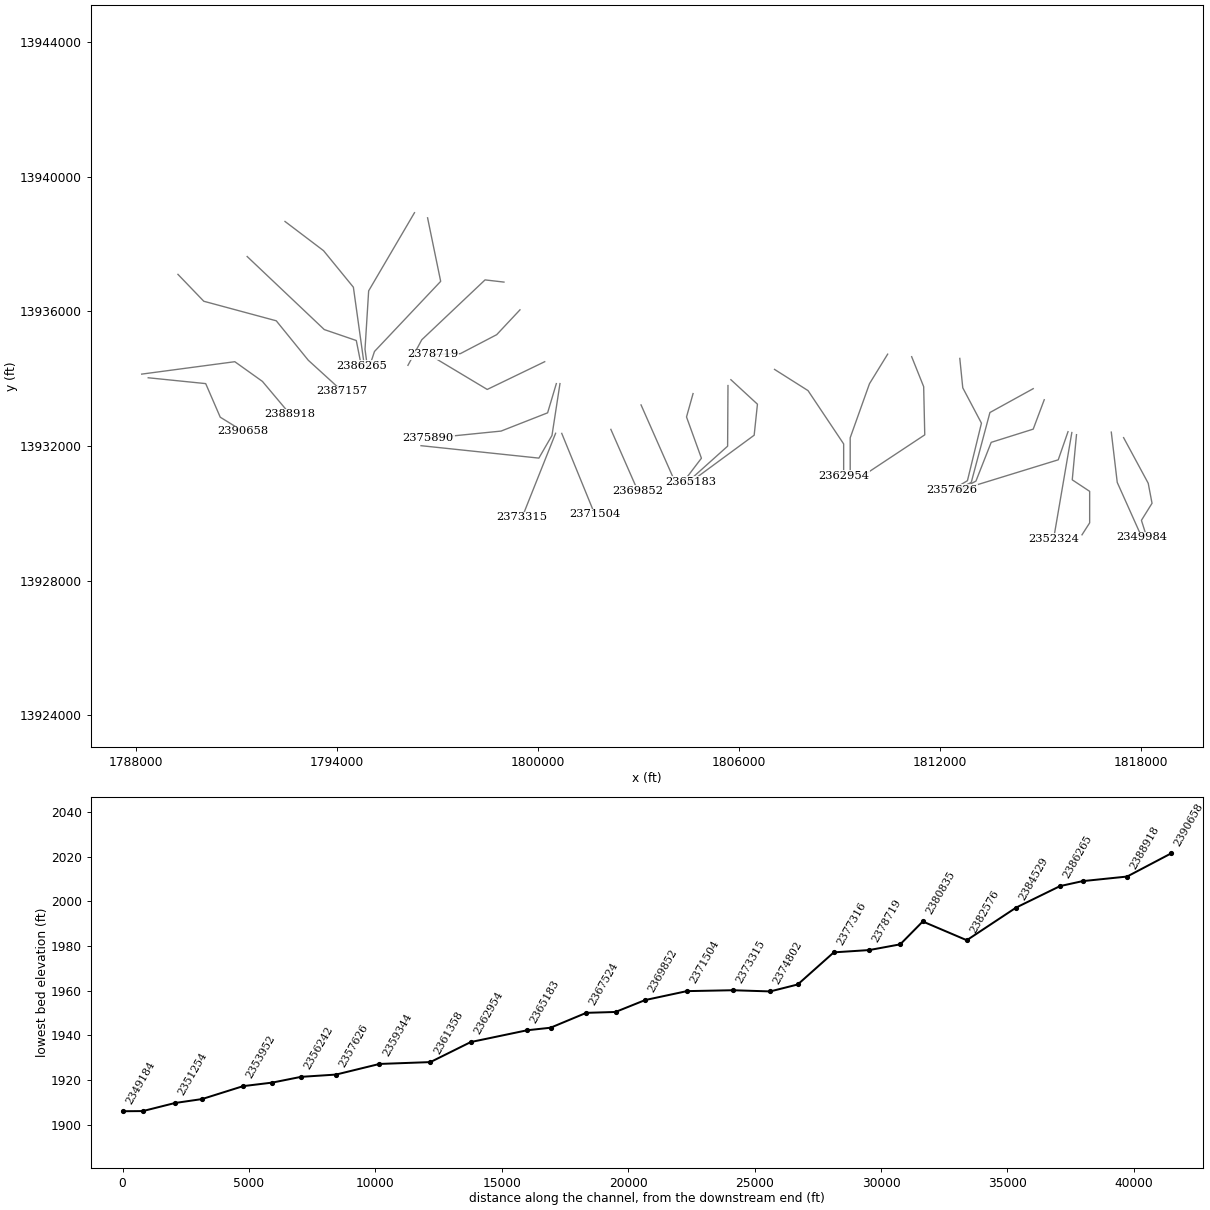
HEC-RAS study Guadalupe River.prj: Guadalupe River Base Level Engineering

--- Guadalupe River.g01 (geometry) --- (continued)

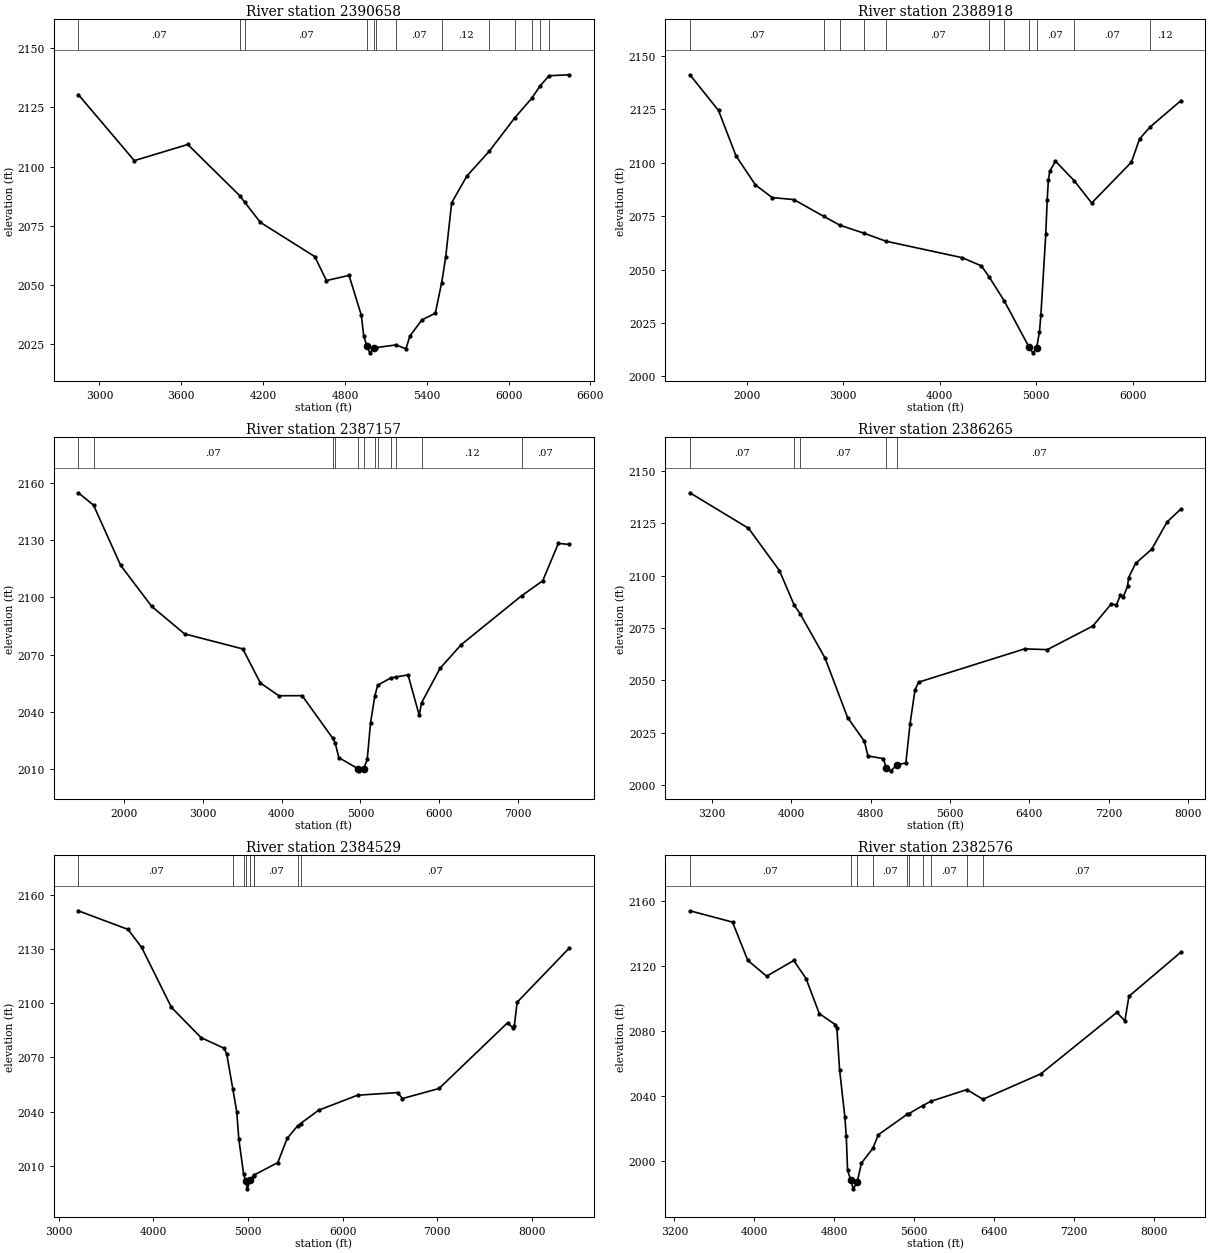
Type RM Length L Ch R = 1 ,2390658 ,1740,1740,1740
BEGIN DESCRIPTION:
Guadalupe River - 259
END DESCRIPTION:
XS GIS Cut Line= 4
      1788376.03     13934029.47      1790090.45     13933855.86
      1790524.48      13932857.6      1791197.25     13932445.25
#Sta/Elev= 30
  2844.6 2130.39  3255.7 2102.51  3647.7 2109.32  4028.2 2087.75  4064.4 2085.01
  4180.4 2076.45  4579.6    2062  4664.2 2051.91  4830.4 2054.09  4920.4 2037.29
  4938.4 2028.42  4961.3 2024.29  4982.5 2021.42  5014.2 2023.37    5030 2023.64
    5176 2024.77    5247  2023.1  5277.5 2028.57  5364.2 2035.29  5462.9 2038.14
  5509.6 2050.97  5539.2 2061.77  5582.8 2084.71    5694 2095.99  5859.4 2106.52
  6045.3 2120.53  6169.3 2128.76  6232.6  2134.1  6297.2 2138.33  6445.4 2138.73
#Mann= 13 ,-1 , 0
  2844.6     .07       0  4028.2     .05       0  4064.4     .07       0
  4961.3     .04       0  5014.2     .07       0    5030     .12       0
    5176     .07       0  5509.6     .12       0  5859.4     .07       0
  6045.3     .12       0  6169.3     .07       0  6232.6     .12       0
  6297.2     .07       0
Bank Sta=4961.3,5014.2
XS Rating Curve= 0 ,0
Exp/Cntr=0.3,0.1

Type RM Length L Ch R = 1 ,2388918 ,1761,1761,1761
BEGIN DESCRIPTION:
Guadalupe River - 258
END DESCRIPTION:
XS GIS Cut Line= 4
       1788180.7     13934137.98      1790958.51      13934506.9
      1791783.16     13933920.97      1792607.81      13932944.4
#Sta/Elev= 30
  1409.6 2141.24  1706.5 2124.53  1888.1 2103.26  2089.8 2089.65  2263.4 2083.76
  2488.3 2082.81  2799.2 2074.92    2966 2070.82  3215.2 2067.07  3443.8 2063.32
    4232 2055.64  4432.7 2051.79    4512 2046.72    4670 2035.39  4928.4 2013.63
  4966.9 2011.07  5005.8 2013.34  5035.4 2021.03  5050.1 2028.98  5100.6 2066.69
  5115.3 2082.73  5127.6 2092.04  5142.4 2096.13  5201.1  2100.8  5395.4 2091.65
  5576.5  2081.2  5988.7 2100.32  6073.2 2111.21  6179.5 2116.69  6501.6  2129.1
#Mann= 11 ,-1 , 0
  1409.6     .07       0  2799.2     .12       0    2966     .07       0
  3215.2     .12       0  3443.8     .07       0    4512     .12       0
    4670     .07       0  4928.4     .04       0  5005.8     .07       0
  5395.4     .07       0  6179.5     .12       0
Bank Sta=4928.4,5005.8
XS Rating Curve= 0 ,0
Exp/Cntr=0.3,0.1

Type RM Length L Ch R = 1 ,2387157 ,892,892,892
BEGIN DESCRIPTION:
Guadalupe River - 257
END DESCRIPTION:
XS GIS Cut Line= 5
      1789262.77     13937101.54      1790033.62     13936302.91
      1792195.48     13935722.18      1793150.35     13934550.31
      1794165.16     13933629.66
#Sta/Elev= 30
  1419.9 2154.87  1613.3  2148.4  1956.6 2116.87  2352.5 2095.23  2768.3 2080.87
  3507.3 2072.97  3731.6 2055.05  3966.3  2048.4  4260.5 2048.45    4651 2025.99
  4679.6 2023.67  4726.4 2015.94  4974.8 2010.02  4976.3 2009.02  5041.6 2010.02
  5086.4 2014.98  5128.1 2034.02  5183.1 2048.28  5219.3 2053.93  5383.9 2057.73
  5447.3  2058.2  5604.2 2059.36  5746.4 2038.21  5775.8  2044.7  6009.9 2062.75
  6279.7 2075.23  7045.5 2100.85  7313.3 2108.68    7512 2128.33  7650.2 2127.76
#Mann= 12 ,-1 , 0
  1419.9     .05       0  1613.3     .07       0    4651     .05       0
  4679.6     .07       0  4974.8     .05       0  5041.6     .07       0
  5183.1     .12       0  5219.3     .07       0  5383.9     .12       0
  5447.3     .07       0  5775.8     .12       0  7045.5     .07       0
Bank Sta=4974.8,5041.6
XS Rating Curve= 0 ,0
Exp/Cntr=0.3,0.1

Type RM Length L Ch R = 1 ,2386265 ,1736,1736,1736
BEGIN DESCRIPTION:
Guadalupe River - 256
END DESCRIPTION:
XS GIS Cut Line= 4
       1791327.4     13937631.93      1793627.78     13935461.76
      1794582.64     13935136.24      1794734.21     13934378.37
#Sta/Elev= 30
    2981 2139.67  3571.2 2122.71  3882.7  2102.5  4031.3 2085.97    4091 2081.88
  4342.3 2060.66  4568.9 2032.27  4738.4 2020.93    4774 2013.91  4929.8 2012.62
    4957  2008.2  5003.9  2006.8    5071 2009.82  5155.9 2010.52  5198.4 2029.34
  5247.8 2045.47  5283.4 2049.16  6351.9 2065.08  6580.9 2064.72  7038.6 2075.99
    7225 2086.59    7276 2085.99  7316.8 2090.87  7342.5  2089.7  7388.1 2094.93
  7398.6 2099.14  7469.7 2105.93  7632.9 2112.77  7785.9 2125.72  7925.2  2131.9
#Mann= 5 ,-1 , 0
    2981     .07       0  4031.3     .05       0    4091     .07       0
    4957     .04       0    5071     .07       0
Bank Sta=4957,5071
XS Rating Curve= 0 ,0
Exp/Cntr=0.3,0.1

Type RM Length L Ch R = 1 ,2384529 ,1953,1953,1953
BEGIN DESCRIPTION:
Guadalupe River - 255
END DESCRIPTION:
XS GIS Cut Line= 4
      1792455.92     13938673.56      1793606.08     13937805.51
      1794495.83     13936720.44      1794821.24     13934399.23
#Sta/Elev= 30
  3207.7 2151.12  3733.6 2140.79  3877.2 2130.85  4191.5 2097.69  4505.8 2080.88
  4747.9 2075.03  4776.6  2071.8  4840.1 2052.67  4882.1 2039.87  4904.3 2024.69
  4954.2 2005.63  4974.7 2001.76  4993.9  1997.2  5024.4  2002.2  5059.7 2004.53
  5065.4 2004.84  5316.3 2011.74  5415.3 2025.14  5525.7 2032.09    5557 2033.36
    5749 2040.76  6158.7 2049.02  6581.8 2050.48    6633 2047.18    7020 2052.75
  7743.7  2089.1  7804.3 2086.12    7815 2087.17  7844.7 2100.47  8395.8 2130.48
#Mann= 9 ,-1 , 0
  3207.7     .07       0  4840.1     .05       0  4954.2     .07       0
  4974.7     .04       0  5024.4     .07       0  5059.7     .05       0
  5065.4     .07       0  5525.7     .12       0    5557     .07       0
Bank Sta=4974.7,5024.4
XS Rating Curve= 0 ,0
Exp/Cntr=0.3,0.1

Type RM Length L Ch R = 1 ,2382576 ,1741,1741,1741
BEGIN DESCRIPTION:
Guadalupe River - 254
END DESCRIPTION:
XS GIS Cut Line= 4
      1796318.76     13938934.01      1794951.56     13936611.94
      1794843.05     13934875.83      1794908.05     13934399.21
#Sta/Elev= 30
  3354.3 2154.07  3781.1 2147.09  3933.4 2123.54  4122.7 2113.72  4394.1 2123.42
  4517.1  2112.3  4649.9 2090.63  4809.9 2083.88  4825.6 2081.94  4852.9 2056.06
  4905.6    2027  4919.8 2015.31  4932.9 1994.01  4964.2 1988.12  4990.4 1982.59
  5028.6 1986.57  5071.5 1998.46    5186 2007.58  5241.4 2015.97  5530.5  2028.6
  5546.4 2028.93  5685.1 2033.92  5766.9 2036.57  6127.9  2043.8  6287.1 2037.82
  6867.5 2053.51    7629  2091.4  7709.1 2086.15  7749.2 2101.31  8269.5 2128.54
#Mann= 10 ,-1 , 0
  3354.3     .07       0  4964.2     .04       0  5028.6     .07       0
    5186     .07       0  5530.5     .05       0  5546.4     .07       0
  5685.1     .05       0  5766.9     .07       0  6127.9     .12       0
  6287.1     .07       0
Bank Sta=4964.2,5028.6
XS Rating Curve= 0 ,0
Exp/Cntr=0.3,0.1

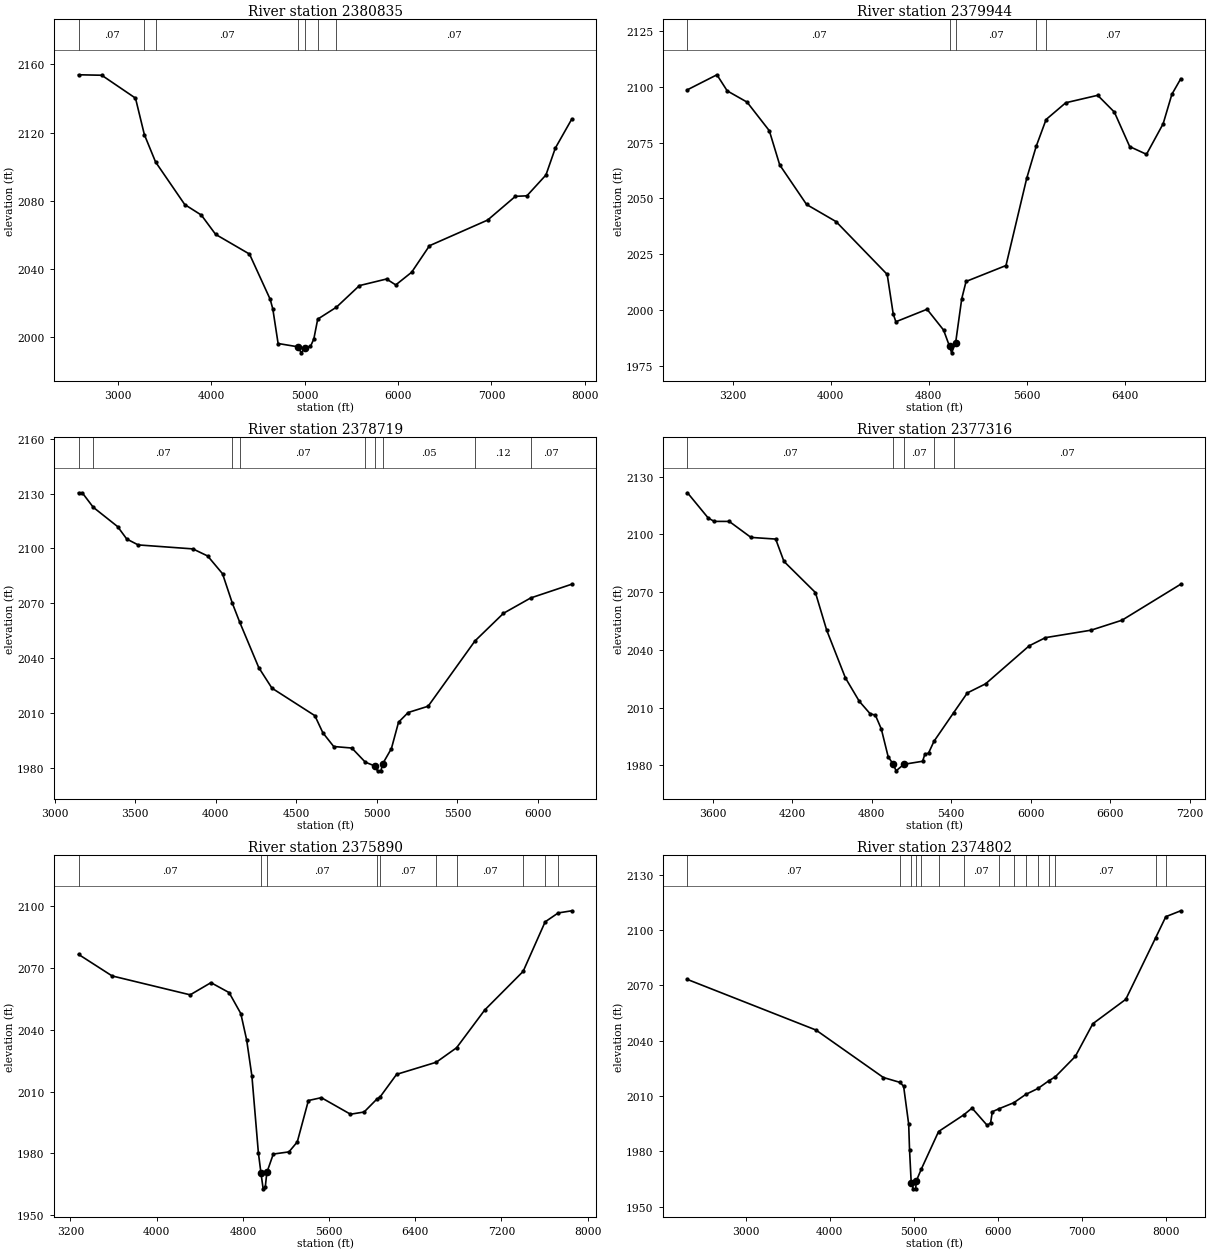
Type RM Length L Ch R = 1 ,2380835 ,891,891,891
BEGIN DESCRIPTION:
Guadalupe River - 253
END DESCRIPTION:
XS GIS Cut Line= 4
      1796709.37     13938782.09        1797100.     13936894.06
      1795125.17     13934810.72      1794973.26     13934354.97
#Sta/Elev= 30
    2581 2153.83  2829.6 2153.56  3190.7 2140.14  3285.8 2118.75  3405.6 2102.75
    3718 2077.81  3895.3 2071.66  4048.5 2060.35  4410.7 2048.82    4632 2022.35
  4660.3 2016.68  4716.9 1996.44  4929.3  1994.5  4964.8 1990.97  5000.1  1993.8
  5063.6 1994.74  5099.2 1999.09  5140.8  2010.7  5341.4 2017.72    5587 2030.35
    5877 2034.21  5976.1 2030.75    6146 2038.17    6337 2053.71  6959.5 2068.74
  7256.4 2082.63  7379.6 2082.94  7583.2 2095.13  7683.3 2110.84    7860 2127.91
#Mann= 7 ,-1 , 0
    2581     .07       0  3285.8     .05       0  3405.6     .07       0
  4929.3     .04       0  5000.1     .07       0  5140.8     .05       0
  5341.4     .07       0
Bank Sta=4929.3,5000.1
XS Rating Curve= 0 ,0
Exp/Cntr=0.3,0.1

Type RM Length L Ch R = 1 ,2379944 ,1225,1225,1225
BEGIN DESCRIPTION:
Guadalupe River - 252
END DESCRIPTION:
XS GIS Cut Line= 4
      1798988.05     13936872.35      1798423.78     13936937.46
      1796535.76     13935157.94      1796123.88     13934399.22
#Sta/Elev= 30
  2831.8 2098.67  3072.2 2105.38  3156.1 2098.17  3318.1 2093.13  3499.7 2080.31
  3584.6 2064.98  3803.9 2047.24  4044.2 2039.58  4461.8  2015.9  4511.2 1998.12
  4532.6 1994.68  4787.1 2000.28  4921.8 1990.97  4971.1  1983.6  4987.5 1980.75
  5020.5 1985.34  5070.3 2005.04  5105.5 2012.75  5431.2 2019.88  5600.7 2059.03
  5677.8  2073.3  5758.6 2085.33  5919.1 2092.84  6179.7 2096.18  6315.7 2088.66
  6441.1 2073.19    6578 2069.73  6713.9 2083.42  6785.2 2096.64  6857.6 2103.59
#Mann= 5 ,-1 , 0
  2831.8     .07       0  4971.1     .04       0  5020.5     .07       0
  5677.8     .12       0  5758.6     .07       0
Bank Sta=4971.1,5020.5
XS Rating Curve= 0 ,0
Exp/Cntr=0.3,0.1

Type RM Length L Ch R = 1 ,2378719 ,1403,1403,1403
BEGIN DESCRIPTION:
Guadalupe River - 251
END DESCRIPTION:
XS GIS Cut Line= 4
      1799465.44     13936047.69      1798771.01     13935309.85
      1797685.94     13934745.62      1796861.26     13934723.92
#Sta/Elev= 30
  3148.2 2130.41  3171.6 2130.39  3239.6 2122.48  3390.9 2111.89  3447.6 2105.09
  3518.4 2101.87  3857.8 2099.69  3949.6 2095.81  4041.9  2086.1  4102.5 2070.02
  4147.8 2059.74  4266.8  2034.7  4348.5 2023.46  4614.9 2008.39  4664.7    1999
  4731.8 1991.51  4844.5 1990.67    4928 1982.93  4985.1 1980.92  5003.9 1978.19
  5024.5 1978.19  5036.1 1982.11    5090 1990.39  5134.2 2004.82  5193.9 2010.12
  5317.9 2013.56  5608.5  2049.3  5785.5 2064.44  5954.3 2072.83  6209.4 2080.36
#Mann= 9 ,-1 , 0
  3148.2     .12       0  3239.6     .07       0  4102.5     .05       0
  4147.8     .07       0    4928     .05       0  4985.1     .04       0
  5036.1     .05       0  5608.5     .12       0  5954.3     .07       0
Bank Sta=4985.1,5036.1
XS Rating Curve= 0 ,0
Exp/Cntr=0.3,0.1

Type RM Length L Ch R = 1 ,2377316 ,1426,1426,1426
BEGIN DESCRIPTION:
Guadalupe River - 250
END DESCRIPTION:
XS GIS Cut Line= 3
      1800203.27     13934506.89      1798488.89     13933682.25
      1796926.43     13934615.39
#Sta/Elev= 30
  3410.2 2121.55  3566.8 2108.44  3612.1 2106.69  3725.3 2106.68  3889.2 2098.38
  4075.8 2097.51  4138.2 2085.92  4375.6 2069.75  4460.6 2050.23  4601.9 2025.44
  4706.6 2013.29  4788.5 2006.81  4828.2 2006.07    4873 1998.88  4924.3 1984.57
  4961.8 1980.66  4984.7 1977.16    5043 1980.55  5184.3 1982.13  5201.4 1985.72
  5229.6 1986.41  5270.1 1992.47  5418.4 2007.32  5521.9 2017.61    5660 2022.35
  5988.8 2042.08  6111.4 2046.32  6455.8  2050.2  6689.3 2055.38  7132.5 2074.08
#Mann= 5 ,-1 , 0
  3410.2     .07       0  4961.8     .04       0    5043     .07       0
  5270.1     .05       0  5418.4     .07       0
Bank Sta=4961.8,5043
XS Rating Curve= 0 ,0
Exp/Cntr=0.3,0.1

Type RM Length L Ch R = 1 ,2375890 ,1088,1088,1088
BEGIN DESCRIPTION:
Guadalupe River - 249
END DESCRIPTION:
XS GIS Cut Line= 4
      1800550.51     13933855.84       1800290.1     13932987.81
      1798901.21     13932445.27      1796731.09     13932228.26
#Sta/Elev= 30
  3274.5 2076.58  3586.4 2066.11  4310.9 2056.94  4503.7 2062.85  4672.1 2058.03
  4780.7 2047.86    4835 2035.06    4884 2017.43  4943.7 1980.37  4968.2 1970.32
  4988.2  1962.8  5008.1  1963.8  5022.5 1970.74  5082.2 1979.68  5227.6 1980.73
  5304.9 1985.57  5408.1 2005.66  5528.2 2007.04  5798.7 1999.01  5925.1 2000.08
  6042.6  2006.3  6072.2  2007.3  6226.6 2018.35  6594.7 2024.23  6783.2 2031.25
  7044.9  2049.6    7401 2068.31  7605.4 2092.36  7726.5 2096.68  7852.8 2097.73
#Mann= 10 ,-1 , 0
  3274.5     .07       0  4968.2     .04       0  5022.5     .07       0
  6042.6     .12       0  6072.2     .07       0  6594.7     .12       0
  6783.2     .07       0    7401     .12       0  7605.4     .07       0
  7726.5     .12       0
Bank Sta=4968.2,5022.5
XS Rating Curve= 0 ,0
Exp/Cntr=0.3,0.1

Type RM Length L Ch R = 1 ,2374802 ,1487,1487,1487
BEGIN DESCRIPTION:
Guadalupe River - 248
END DESCRIPTION:
XS GIS Cut Line= 4
      1800659.02     13933855.84      1800420.31     13932315.06
      1800029.69     13931642.32      1796514.07     13932011.24
#Sta/Elev= 30
  2306.3 2073.26  3835.2 2045.85  4638.6 2020.08  4835.6 2017.44  4879.4 2015.31
  4939.7 1994.73  4949.7 1980.98  4969.9 1962.84  4995.3 1959.69    5023 1959.69
  5030.2 1963.99  5089.2 1970.32  5295.6 1990.79    5594 1999.78  5693.8 2003.49
  5874.8 1994.09    5915 1995.52  5935.1 2001.52  6016.3 2003.16  6190.9  2006.4
  6333.5 2010.91  6478.6 2014.14  6608.2 2018.31  6685.7 2020.49  6923.2 2031.52
  7131.7 2049.26  7523.8 2062.48  7878.4 2095.78  8000.5 2107.32  8178.3 2110.52
#Mann= 15 ,-1 , 0
  2306.3     .07       0  4835.6     .12       0  4969.9     .04       0
  5030.2     .07       0  5089.2     .07       0  5295.6     .05       0
    5594     .07       0  6016.3     .12       0  6190.9     .07       0
  6333.5     .12       0  6478.6     .07       0  6608.2     .12       0
  6685.7     .07       0  7878.4     .12       0  8000.5     .07       0
Bank Sta=4969.9,5030.2
XS Rating Curve= 0 ,0
Exp/Cntr=0.3,0.1

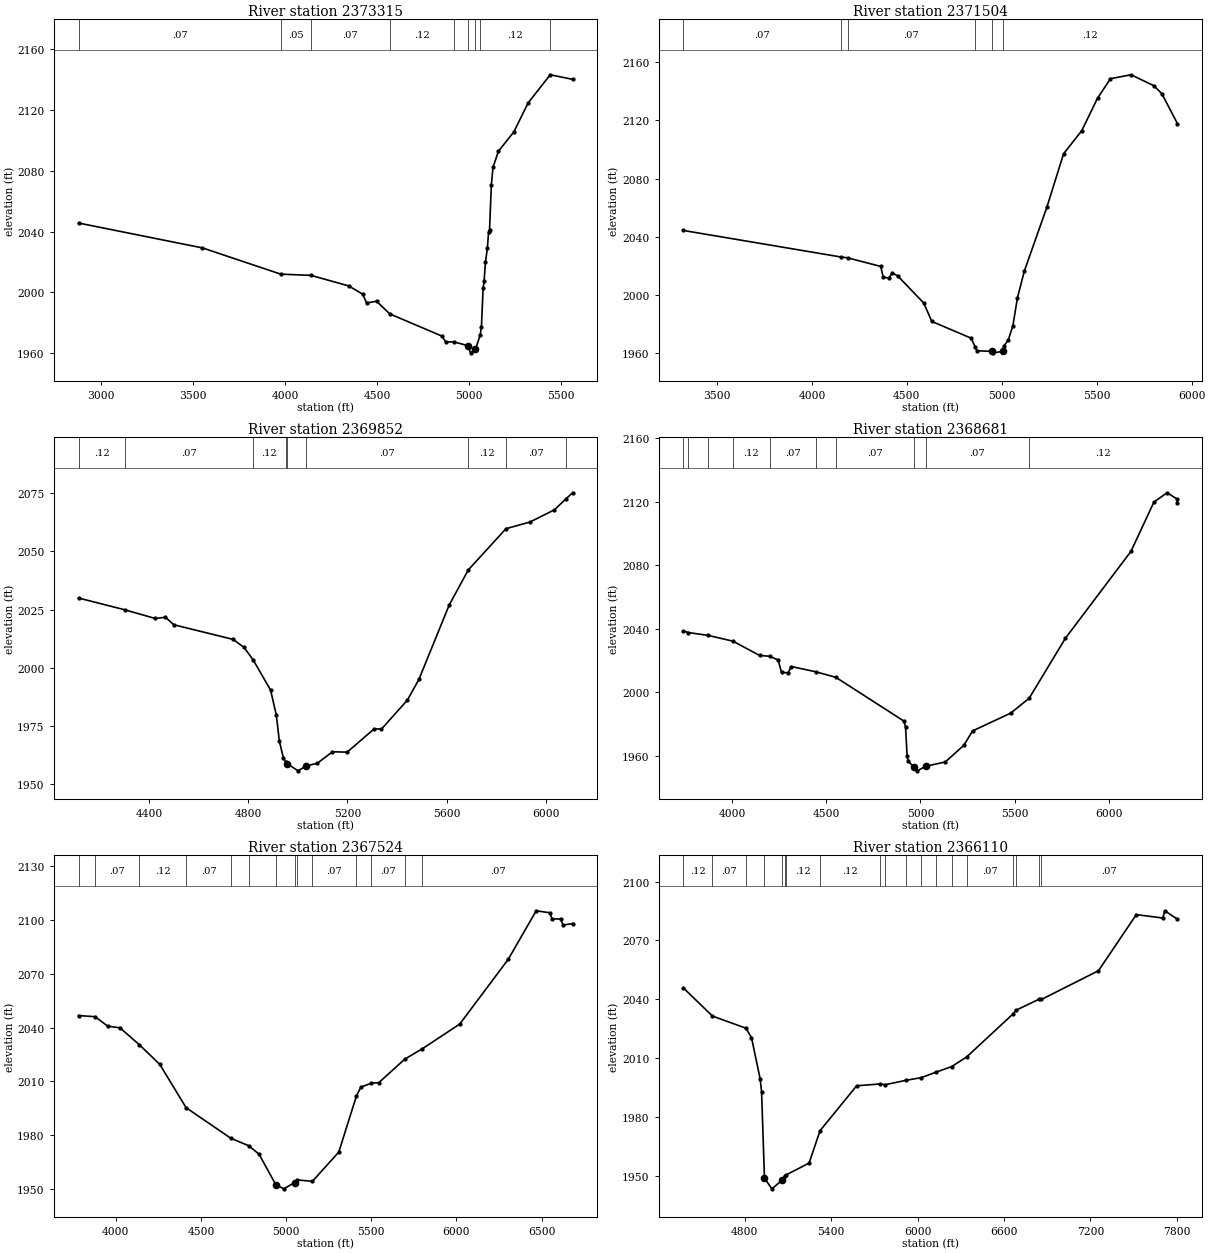
Type RM Length L Ch R = 1 ,2373315 ,1811,1811,1811
BEGIN DESCRIPTION:
Guadalupe River - 247
END DESCRIPTION:
XS GIS Cut Line= 2
      1800528.82     13932380.17      1799530.56     13929884.52
#Sta/Elev= 30
  2876.3 2045.68  3550.6  2029.3  3976.3 2012.03  4140.5 2011.23  4346.6 2004.26
    4422 1998.83  4443.6 1993.02  4497.4  1994.2  4569.6 1985.86  4852.8 1971.27
  4874.4 1967.35  4918.2 1967.45  4992.9 1964.98  5008.8 1960.22  5035.9 1962.55
  5061.4 1971.99  5068.2 1977.42  5077.3 2002.62  5082.7 2007.26  5089.8  2019.7
  5100.6 2029.15    5107 2039.64  5112.3 2041.11  5122.1 2070.74  5131.2 2082.37
  5160.8 2092.99  5244.3 2105.64  5322.4 2124.79  5442.5 2143.29  5564.2 2140.28
#Mann= 9 ,-1 , 0
  2876.3     .07       0  3976.3     .05       0  4140.5     .07       0
  4569.6     .12       0  4918.2     .07       0  4992.9     .04       0
  5035.9     .07       0  5061.4     .12       0  5442.5     .07       0
Bank Sta=4992.9,5035.9
XS Rating Curve= 0 ,0
Exp/Cntr=0.3,0.1

Type RM Length L Ch R = 1 ,2371504 ,1652,1652,1652
BEGIN DESCRIPTION:
Guadalupe River - 246
END DESCRIPTION:
XS GIS Cut Line= 2
      1800712.02     13932376.55      1801698.94     13929968.87
#Sta/Elev= 30
    3323 2044.18  4151.8 2025.91  4187.9 2025.32  4362.2 2019.39  4375.4    2012
  4405.4 2011.38  4423.3    2015  4452.7 2012.73  4589.2 1994.13  4631.5 1981.45
  4837.7 1969.99  4859.8 1964.03    4869 1961.26    4947 1960.82  4955.3 1959.82
  5004.6 1960.82  5010.6 1964.36  5034.6 1968.82  5058.5 1978.49  5082.5 1997.71
  5118.7 2016.15  5237.3 2060.13  5325.5 2097.04  5421.3 2112.99  5504.2 2135.35
  5572.6 2148.81  5680.7  2151.5  5800.5    2144  5842.8 2138.52  5925.1 2117.87
#Mann= 6 ,-1 , 0
    3323     .07       0  4151.8     .12       0  4187.9     .07       0
  4859.8     .12       0    4947     .04       0  5004.6     .12       0
Bank Sta=4947,5004.6
XS Rating Curve= 0 ,0
Exp/Cntr=0.3,0.1

Type RM Length L Ch R = 1 ,2369852 ,1171,1171,1171
BEGIN DESCRIPTION:
Guadalupe River - 245
END DESCRIPTION:
XS GIS Cut Line= 2
      1802176.86     13932495.91       1802979.8     13930673.02
#Sta/Elev= 30
  4116.2 2030.01  4303.5 2024.93  4425.2 2021.23  4466.4 2021.75  4500.6 2018.52
  4739.4 2012.25  4783.8 2008.77    4820 2003.47  4890.3 1990.51  4913.6 1979.73
  4925.8 1968.53  4942.4 1961.22  4950.9 1959.75  4958.6 1958.85    5001 1955.82
  5035.1 1957.97  5078.8 1959.06    5140 1964.01    5199 1963.84  5308.3 1973.85
  5337.6 1973.76  5441.8 1986.16  5488.5 1995.09  5610.6 2027.02  5687.6 2042.08
  5839.5 2059.78  5935.8 2062.62  6034.5 2067.86  6080.8 2072.53  6108.1 2075.19
#Mann= 9 ,-1 , 0
  4116.2     .12       0  4303.5     .07       0    4820     .12       0
  4950.9     .07       0  4958.6     .04       0  5035.1     .07       0
  5687.6     .12       0  5839.5     .07       0  6080.8     .12       0
Bank Sta=4958.6,5035.1
XS Rating Curve= 0 ,0
Exp/Cntr=0.3,0.1

Type RM Length L Ch R = 1 ,2368681 ,1157,1157,1157
BEGIN DESCRIPTION:
Guadalupe River - 244
END DESCRIPTION:
XS GIS Cut Line= 2
      1803077.47      13933222.9      1804140.43     13930825.81
#Sta/Elev= 30
  3741.6 2038.65    3768 2037.65  3874.2 2035.82  4005.4 2032.19    4146 2023.21
  4198.8 2022.72  4244.6 2020.35  4262.4  2012.5  4297.2 2012.31  4314.4 2016.24
  4445.4  2012.9  4551.4  2009.4  4911.3 1981.91  4920.7  1978.3  4929.1    1960
  4934.5  1956.5  4964.5 1953.03  4983.3  1950.5  5027.6 1953.37  5131.7 1956.09
  5230.2 1966.58  5276.8 1975.68  5479.4 1986.89  5576.9 1996.25  5769.6 2034.12
  6117.3 2088.83  6239.1 2119.88    6309 2125.73    6361  2121.9  6363.8 2119.38
#Mann= 10 ,-1 , 0
  3741.6     .07       0    3768     .12       0  3874.2     .07       0
  4005.4     .12       0  4198.8     .07       0  4445.4     .12       0
  4551.4     .07       0  4964.5     .04       0  5027.6     .07       0
  5576.9     .12       0
Bank Sta=4964.5,5027.6
XS Rating Curve= 0 ,0
Exp/Cntr=0.3,0.1

Type RM Length L Ch R = 1 ,2367524 ,1414,1414,1414
BEGIN DESCRIPTION:
Guadalupe River - 243
END DESCRIPTION:
XS GIS Cut Line= 4
       1804629.1     13933559.23       1804433.8     13932864.83
      1804878.68      13931638.7      1804346.99     13930944.25
#Sta/Elev= 30
  3781.6 2046.77  3879.4 2046.14  3952.2 2040.88  4024.9 2039.93  4137.9 2030.55
  4258.4 2019.54    4413 1995.37  4675.3 1978.34  4780.6 1974.16  4840.7 1969.49
  4938.9 1952.53  4986.8 1950.11  5049.7 1953.61  5066.7 1955.07  5154.5 1954.29
  5309.3 1970.64  5412.7 2001.84  5438.9 2006.86  5501.2 2009.07  5543.6 2009.29
  5696.9 2022.49  5800.4  2028.3  6019.4 2042.03    6304 2078.14  6468.1 2105.23
    6547 2104.14  6561.6 2100.71  6611.4 2100.63  6625.9 2097.27  6681.9  2098.1
#Mann= 14 ,-1 , 0
  3781.6     .12       0  3879.4     .07       0  4137.9     .12       0
    4413     .07       0  4675.3     .12       0  4780.6     .07       0
  4938.9     .04       0  5049.7     .07       0  5066.7     .12       0
  5154.5     .07       0  5412.7     .12       0  5501.2     .07       0
  5696.9     .12       0  5800.4     .07       0
Bank Sta=4938.9,5049.7
XS Rating Curve= 0 ,0
Exp/Cntr=0.3,0.1

Type RM Length L Ch R = 1 ,2366110 ,927,927,927
BEGIN DESCRIPTION:
Guadalupe River - 242
END DESCRIPTION:
XS GIS Cut Line= 3
      1805670.78     13933798.03      1805659.93     13931996.78
      1804444.64      13930911.7
#Sta/Elev= 30
  4373.1 2045.81  4574.8 2031.47  4807.4 2025.29  4846.1  2020.5  4906.1 1999.51
  4916.1 1992.97  4936.1 1948.89  4987.6 1943.45  5056.1  1947.7  5077.3 1950.23
  5085.6 1950.52  5246.1 1956.56  5321.8 1973.05  5576.2 1995.95  5739.9 1996.89
  5774.7 1996.49  5917.1 1998.72  6025.4  2000.1  6129.2 2002.94  6235.8 2005.73
  6339.4 2010.61  6660.2 2032.42  6682.5 2034.43  6840.2 2039.96  6859.2 2039.93
  7255.4 2054.57  7517.9 2083.14  7701.8 2081.43    7716 2085.11  7803.6 2080.83
#Mann= 19 ,-1 , 0
  4373.1     .12       0  4574.8     .07       0  4807.4     .12       0
  4936.1     .04       0  5056.1     .05       0  5077.3     .07       0
  5085.6     .12       0  5321.8     .12       0  5739.9     .07       0
  5774.7     .12       0  5917.1     .07       0  6025.4     .12       0
  6129.2     .07       0  6235.8     .12       0  6339.4     .07       0
  6660.2     .12       0  6682.5     .07       0  6840.2     .12       0
  6859.2     .07       0
Bank Sta=4936.1,5056.1
XS Rating Curve= 0 ,0
Exp/Cntr=0.3,0.1

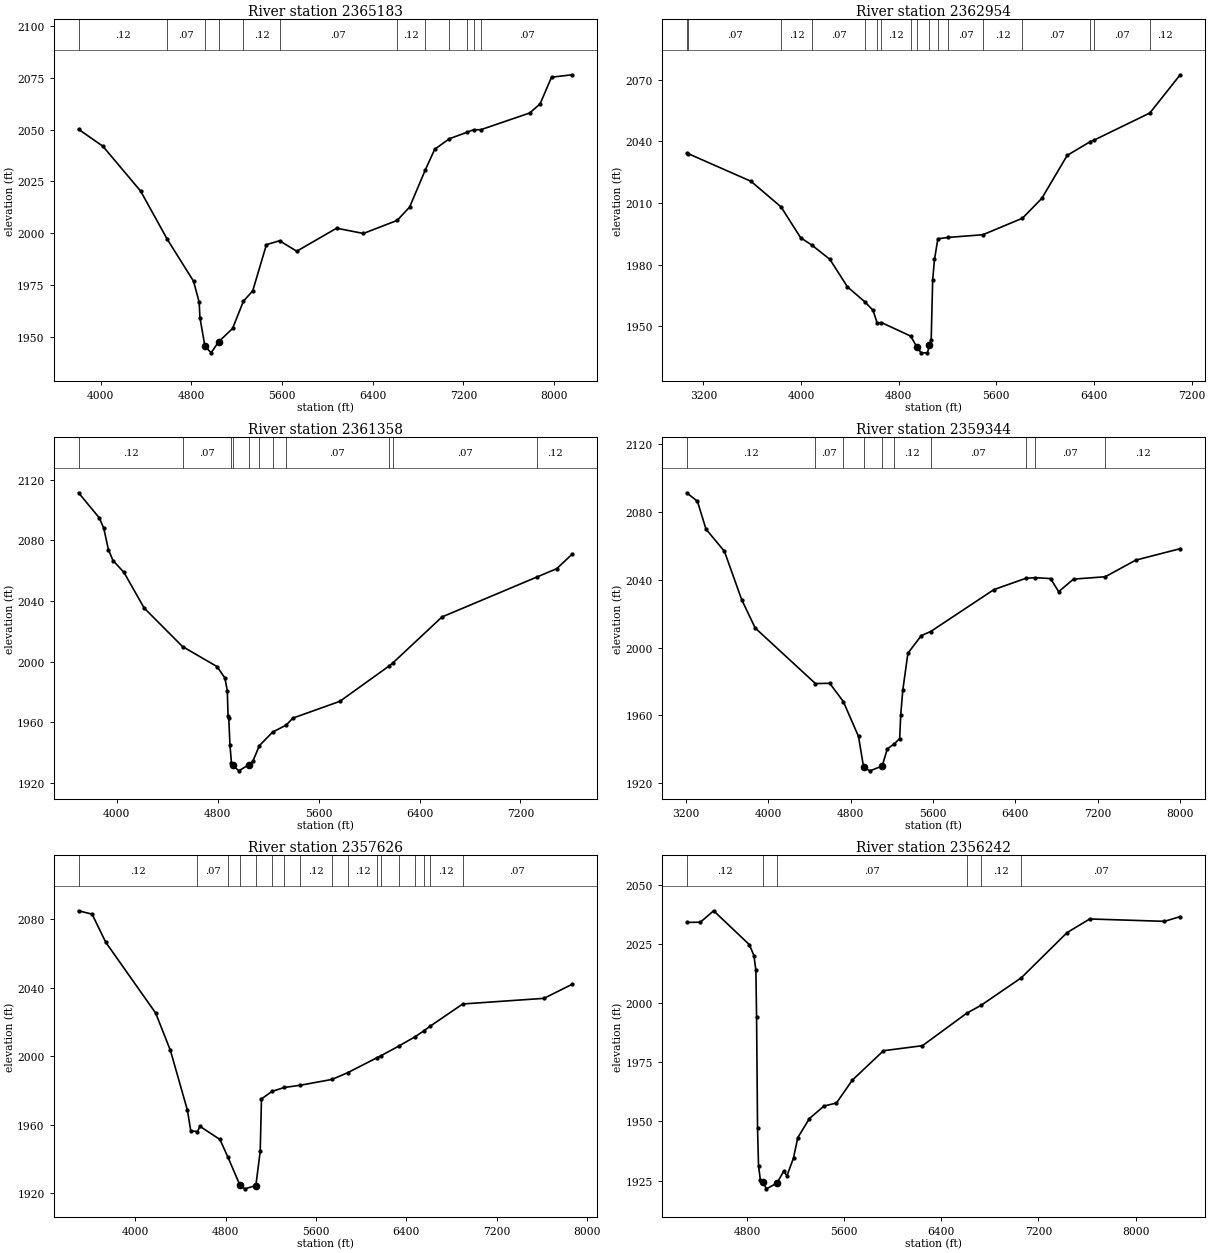
Type RM Length L Ch R = 1 ,2365183 ,2229,2229,2229
BEGIN DESCRIPTION:
Guadalupe River - 241
END DESCRIPTION:
XS GIS Cut Line= 4
      1805757.57     13933971.62      1806549.69     13933244.61
      1806452.03      13932322.3      1804553.19     13930933.43
#Sta/Elev= 30
  3804.4 2050.11  4019.4 2041.93  4352.3 2020.31    4587 1997.12  4819.1 1976.86
    4869 1966.73  4875.6 1959.31  4919.4 1945.65  4974.3 1942.31  5040.1  1947.6
  5163.7 1954.05  5259.9 1967.26  5341.8 1972.21  5462.4 1994.47  5578.2 1996.36
  5730.1 1991.31    6082 2002.41  6318.3 1999.87  6615.7 2006.15    6726 2012.59
  6864.8 2030.54  6947.6 2040.46  7076.7 2045.54  7229.7  2048.6  7289.9 2049.86
  7354.7 2049.91  7785.7 2057.96  7877.5 2062.34  7978.4 2075.22  8159.6 2076.39
#Mann= 12 ,-1 , 0
  3804.4     .12       0    4587     .07       0  4919.4     .04       0
  5040.1     .07       0  5259.9     .12       0  5578.2     .07       0
  6615.7     .12       0  6864.8     .07       0  7076.7     .12       0
  7229.7     .07       0  7289.9     .12       0  7354.7     .07       0
Bank Sta=4919.4,5040.1
XS Rating Curve= 0 ,0
Exp/Cntr=0.3,0.1

Type RM Length L Ch R = 1 ,2362954 ,1596,1596,1596
BEGIN DESCRIPTION:
Guadalupe River - 240
END DESCRIPTION:
XS GIS Cut Line= 4
      1807059.94     13934277.66      1808058.19     13933648.33
      1809121.56     13932064.12      1809121.56     13931109.59
#Sta/Elev= 30
  3063.4 2034.16  3074.4 2033.98  3589.7 2020.52  3836.5 2008.04    3997 1993.03
  4090.3 1989.39  4237.1 1982.49    4380 1969.16  4522.9 1961.85  4589.2 1957.78
  4623.8 1951.58  4658.8 1951.78  4898.7 1945.17  4949.3 1939.84  4984.1 1937.04
  5035.8 1937.04  5051.3 1940.69  5066.3 1943.29  5078.5 1972.51  5093.3  1982.5
  5121.2 1992.52  5207.4  1993.2  5490.2 1994.51  5813.8 2002.53  5972.5  2012.2
  6180.6 2033.12    6371 2039.85  6400.6 2040.53  6857.6 2053.73    7106 2072.32
#Mann= 17 ,-1 , 0
  3063.4     .12       0  3074.4     .07       0  3836.5     .12       0
  4090.3     .07       0  4522.9     .12       0  4623.8     .07       0
  4658.8     .12       0  4898.7     .07       0  4949.3     .04       0
  5051.3     .07       0  5121.2     .12       0  5207.4     .07       0
  5490.2     .12       0  5813.8     .07       0    6371     .05       0
  6400.6     .07       0  6857.6     .12       0
Bank Sta=4949.3,5051.3
XS Rating Curve= 0 ,0
Exp/Cntr=0.3,0.1

Type RM Length L Ch R = 1 ,2361358 ,2014,2014,2014
BEGIN DESCRIPTION:
Guadalupe River - 239
END DESCRIPTION:
XS GIS Cut Line= 4
      1810434.26     13934731.19       1809891.7     13933852.24
      1809316.61     13932246.34      1809316.61     13931074.42
#Sta/Elev= 30
    3698  2111.3  3861.2 2094.91  3897.8 2088.01  3934.5 2073.89  3971.2 2066.64
  4057.8 2058.87  4218.3 2035.33  4522.5 2009.95  4796.2 1996.74  4857.7 1989.26
  4876.7    1981  4883.1 1964.15  4888.4 1963.01  4897.9 1945.04  4910.1 1933.02
  4919.2 1931.92  4968.5 1928.08  5046.6  1932.1  5078.5 1934.25  5130.7 1944.68
  5236.4 1953.64  5342.1 1958.15  5397.2 1962.86  5768.9 1973.88  6155.4 1996.97
  6188.1 1999.13    6578 2029.48  7329.9 2055.79    7488 2061.34  7608.6  2070.8
#Mann= 11 ,-1 , 0
    3698     .12       0  4522.5     .07       0  4910.1     .12       0
  4919.2     .04       0  5046.6     .12       0  5130.7     .07       0
  5236.4     .12       0  5342.1     .07       0  6155.4     .12       0
  6188.1     .07       0  7329.9     .12       0
Bank Sta=4919.2,5046.6
XS Rating Curve= 0 ,0
Exp/Cntr=0.3,0.1

Type RM Length L Ch R = 1 ,2359344 ,1718,1718,1718
BEGIN DESCRIPTION:
Guadalupe River - 238
END DESCRIPTION:
XS GIS Cut Line= 4
      1811150.37     13934655.22      1811508.46     13933765.44
      1811541.01     13932333.15       1809534.1     13931009.68
#Sta/Elev= 30
  3205.6 2091.37    3310 2086.38  3393.3 2069.91  3572.3 2056.84  3739.9 2028.32
  3871.5 2011.55  4456.8 1978.76  4595.3 1978.93  4727.7 1968.17  4875.4 1947.55
  4925.4 1929.23  4987.6 1927.25  5105.4  1930.1  5155.4 1940.25  5221.2 1943.05
  5275.5  1946.3  5285.5 1960.15  5305.5 1974.77  5355.5 1996.67  5485.5 2007.05
    5577 2009.49  6191.5 2034.23  6501.7  2040.9  6593.6 2041.26    6742 2040.73
  6820.3 2032.99  6964.8 2040.42  7273.1  2041.8    7570 2051.63  8001.4 2058.37
#Mann= 10 ,-1 , 0
  3205.6     .12       0  4456.8     .07       0  4727.7     .12       0
  4925.4     .04       0  5105.4     .12       0  5221.2     .12       0
    5577     .07       0  6501.7     .12       0  6593.6     .07       0
  7273.1     .12       0
Bank Sta=4925.4,5105.4
XS Rating Curve= 0 ,0
Exp/Cntr=0.3,0.1

Type RM Length L Ch R = 1 ,2357626 ,1384,1384,1384
BEGIN DESCRIPTION:
Guadalupe River - 237
END DESCRIPTION:
XS GIS Cut Line= 5
       1812586.3     13934604.58      1812674.92     13933731.07
      1813231.93     13932680.35      1812814.17     13930971.35
      1812345.76     13930692.84
#Sta/Elev= 30
  3497.6 2084.85  3617.8 2082.88  3738.4  2066.5  4180.7 2025.14  4311.3 2003.34
  4461.7  1968.5  4491.6 1956.44  4550.4 1955.93  4573.9 1958.96  4749.9 1951.32
  4820.5 1941.07  4925.8 1924.85  4970.3  1922.5  5068.4 1924.41  5106.8 1944.32
  5118.1 1975.01  5210.8 1979.37  5320.2 1981.69  5458.2 1982.94    5743 1986.39
  5884.7  1990.4  6143.9 1999.16  6173.3 2000.09  6333.4 2005.83  6479.2  2011.3
  6559.4  2014.9  6611.8 2017.43    6901 2030.44  7620.1 2033.72  7869.1 2041.89
#Mann= 17 ,-1 , 0
  3497.6     .12       0  4550.4     .07       0  4820.5     .12       0
  4925.8     .04       0  5068.4     .12       0  5210.8     .12       0
  5320.2     .07       0  5458.2     .12       0    5743     .05       0
  5884.7     .12       0  6143.9     .07       0  6173.3     .12       0
  6333.4     .07       0  6479.2     .12       0  6559.4     .07       0
  6611.8     .12       0    6901     .07       0
Bank Sta=4925.8,5068.4
XS Rating Curve= 0 ,0
Exp/Cntr=0.3,0.1

Type RM Length L Ch R = 1 ,2356242 ,1137,1137,1137
BEGIN DESCRIPTION:
Guadalupe River - 236
END DESCRIPTION:
XS GIS Cut Line= 4
      1814776.39     13933705.77      1813485.11     13932996.83
       1812928.1     13930920.71      1812537.41     13930719.06
#Sta/Elev= 30
  4304.2 2034.09  4417.1 2034.19  4526.1 2039.01  4819.9  2024.7  4857.8 2020.06
  4873.9 2013.88  4879.6 1993.96  4887.6 1947.25  4895.6 1931.21  4910.4 1925.38
  4933.2 1924.24    4961 1921.48  5048.2 1923.92  5102.2 1928.89  5129.7 1927.01
  5183.7 1934.55  5218.4 1943.09  5314.5 1951.19  5433.9 1956.46  5537.1 1957.77
  5667.9 1967.43  5924.1 1979.86  6245.1 1981.99  6609.4 1995.71  6728.3 1999.08
  7059.2 2010.71  7435.8  2029.8  7622.1 2035.55  8236.7 2034.55  8366.5 2036.54
#Mann= 6 ,-1 , 0
  4304.2     .12       0  4933.2     .04       0  5048.2     .07       0
  6609.4     .07       0  6728.3     .12       0  7059.2     .07       0
Bank Sta=4933.2,5048.2
XS Rating Curve= 0 ,0
Exp/Cntr=0.3,0.1

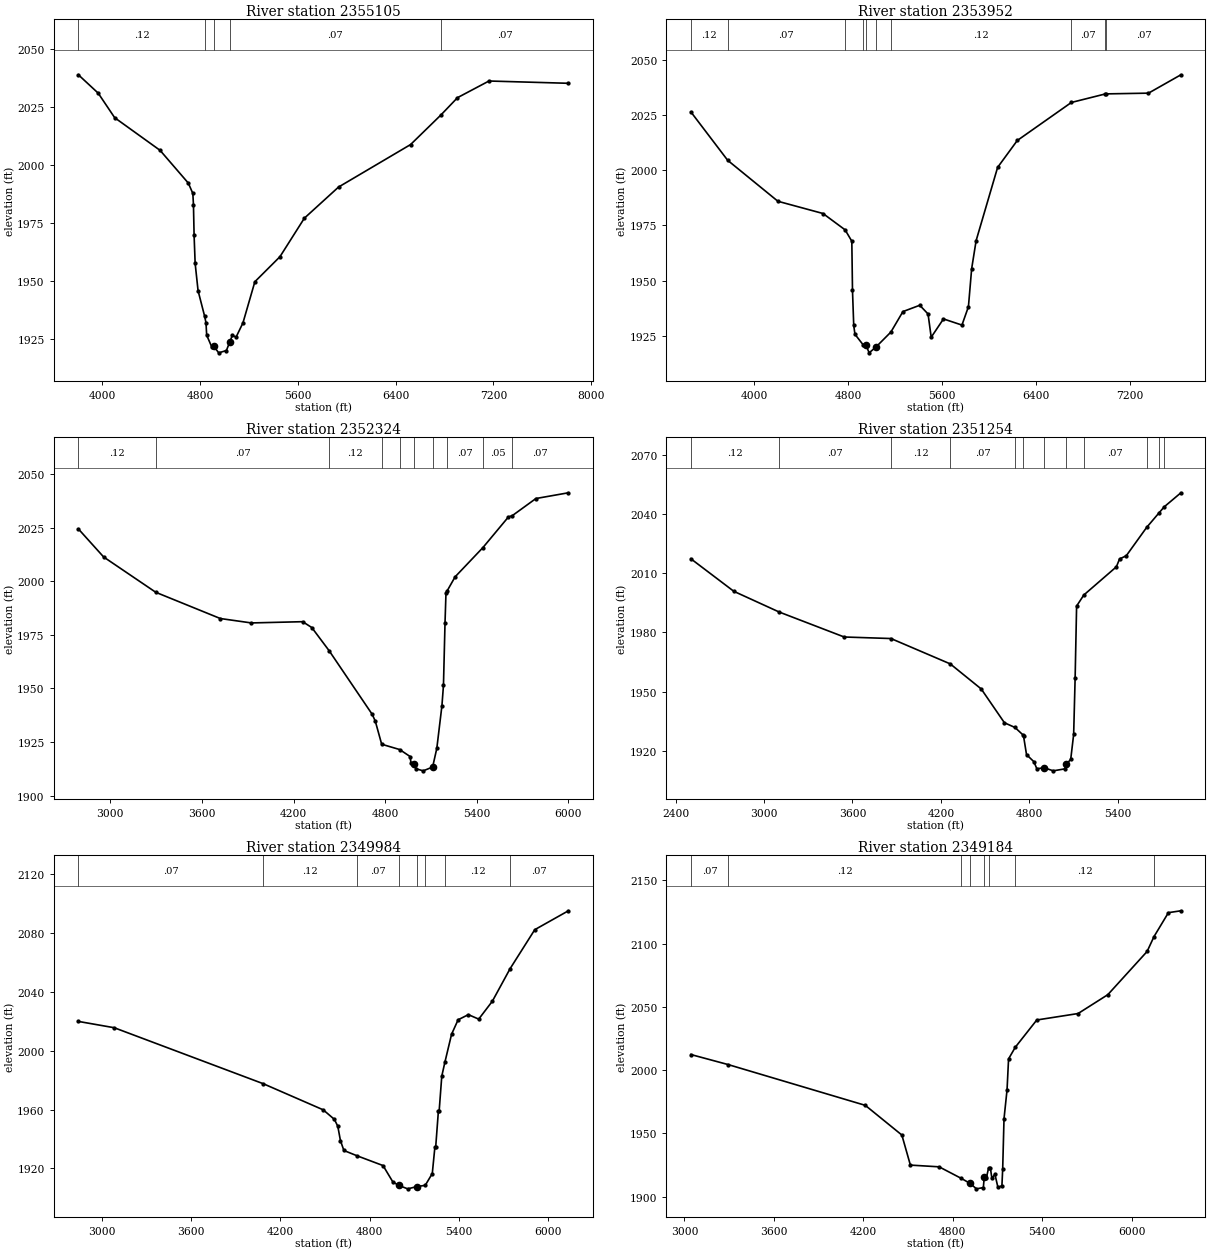
Type RM Length L Ch R = 1 ,2355105 ,1153,1153,1153
BEGIN DESCRIPTION:
Guadalupe River - 235
END DESCRIPTION:
XS GIS Cut Line= 5
       1815105.5     13933376.61      1814776.36     13932503.12
      1813523.09     13932110.68      1813067.36     13930958.69
       1812603.1     13930713.95
#Sta/Elev= 30
  3802.6 2039.03    3965 2031.09    4100 2020.48  4471.3 2006.39  4702.3 1992.25
  4739.4 1987.79  4744.6  1982.9  4749.8 1969.64  4758.4 1957.54  4782.3 1945.76
  4835.9 1934.74  4847.2  1931.9  4852.7 1926.55  4894.6 1921.41  4912.1 1921.68
  4951.1 1918.91  5014.2 1919.91  5041.4 1923.58  5062.3 1926.42  5093.7 1925.73
  5149.7 1931.86  5247.1 1949.63  5452.3 1960.43  5652.2 1977.08    5932 1990.53
  6521.5 2008.89  6769.2 2021.63  6905.4 2029.14  7163.1 2036.34    7813 2035.35
#Mann= 5 ,-1 , 0
  3802.6     .12       0  4835.9     .07       0  4912.1     .04       0
  5041.4     .07       0  6769.2     .07       0
Bank Sta=4912.1,5041.4
XS Rating Curve= 0 ,0
Exp/Cntr=0.3,0.1

Type RM Length L Ch R = 1 ,2353952 ,1628,1628,1628
BEGIN DESCRIPTION:
Guadalupe River - 234
END DESCRIPTION:
XS GIS Cut Line= 3
      1815814.41     13932427.16      1815523.25     13931591.65
      1812384.51     13930629.78
#Sta/Elev= 30
  3463.1 2026.44  3776.3 2004.51  4203.6 1985.96  4586.6 1980.43  4774.9 1973.02
  4831.9 1967.87  4837.6 1945.58  4848.1 1929.77  4858.5 1925.74  4928.7 1920.92
  4952.7 1920.79  4979.3 1917.33  5038.9 1920.05  5163.9 1926.72  5266.5 1936.01
  5409.6 1938.87  5480.3 1934.92    5507  1924.4  5611.3 1932.69  5768.5  1929.9
  5823.6 1938.22  5851.1 1955.45  5889.1 1968.16  6071.8 2001.31  6239.1 2013.49
    6699 2030.71  6987.7 2034.57  6997.7  2034.6    7355 2034.93  7630.7 2043.25
#Mann= 10 ,-1 , 0
  3463.1     .12       0  3776.3     .07       0  4774.9     .12       0
  4928.7     .07       0  4952.7     .04       0  5038.9     .07       0
  5163.9     .12       0    6699     .07       0  6987.7     .05       0
  6997.7     .07       0
Bank Sta=4952.7,5038.9
XS Rating Curve= 0 ,0
Exp/Cntr=0.3,0.1

Type RM Length L Ch R = 1 ,2352324 ,1070,1070,1070
BEGIN DESCRIPTION:
Guadalupe River - 233
END DESCRIPTION:
XS GIS Cut Line= 2
      1815928.34     13932401.82      1815384.26     13929238.57
#Sta/Elev= 30
  2790.5 2024.42  2956.2 2011.32  3297.8 1994.84  3720.2 1982.61  3923.7 1980.55
  4259.6 1981.13  4319.5  1978.4    4433 1967.59  4715.2  1937.9  4735.5 1934.71
  4777.2 1923.95  4894.8 1921.48  4963.6 1918.21  4968.8 1915.36  4989.1 1914.61
  5000.9 1912.54  5049.1 1911.54  5110.9 1913.32  5138.4 1922.06  5171.8 1941.89
  5181.9 1951.41  5192.1 1980.68  5198.3  1994.3  5206.1 1995.52  5258.2 2002.06
  5439.8 2015.67  5607.7 2030.03  5631.8 2030.56  5787.5  2038.6  6000.2 2041.28
#Mann= 10 ,-1 , 0
  2790.5     .12       0  3297.8     .07       0    4433     .12       0
  4777.2     .07       0  4894.8     .12       0  4989.1     .04       0
  5110.9     .12       0  5206.1     .07       0  5439.8     .05       0
  5631.8     .07       0
Bank Sta=4989.1,5110.9
XS Rating Curve= 0 ,0
Exp/Cntr=0.3,0.1

Type RM Length L Ch R = 1 ,2351254 ,1270,1270,1270
BEGIN DESCRIPTION:
Guadalupe River - 232
END DESCRIPTION:
XS GIS Cut Line= 5
       1816067.6     13932338.54      1815941.01     13930996.67
      1816460.04     13930654.87      1816460.04     13929718.08
      1816232.15     13929363.59
#Sta/Elev= 30
  2502.8 2017.31  2794.6 2000.81  3102.5 1990.31  3543.9 1977.65  3861.4 1976.87
  4264.1 1964.01  4474.5 1951.29    4632 1934.15  4703.6 1931.77  4755.7 1928.15
    4762  1927.3    4782 1917.98    4832 1914.42    4852 1910.82    4902 1911.36
  4963.2 1909.78  5042.2 1910.78    5052 1913.12    5082 1915.58    5102 1928.25
    5112 1956.79    5122 1993.33    5171 1998.94    5392 2013.23  5413.7 2017.22
  5459.3 2018.85  5597.7 2033.22  5682.4 2040.65  5717.2 2043.67  5830.3 2050.78
#Mann= 12 ,-1 , 0
  2502.8     .12       0  3102.5     .07       0  3861.4     .12       0
  4264.1     .07       0  4703.6     .12       0  4755.7     .07       0
    4902     .04       0    5052     .07       0    5171     .07       0
  5597.7     .12       0  5682.4     .07       0  5717.2     .12       0
Bank Sta=4902,5052
XS Rating Curve= 0 ,0
Exp/Cntr=0.3,0.1

Type RM Length L Ch R = 1 ,2349984 ,800,800,800
BEGIN DESCRIPTION:
Guadalupe River - 231
END DESCRIPTION:
XS GIS Cut Line= 3
      1817105.65     13932414.55      1817282.89     13930920.71
      1818016.58     13929288.88
#Sta/Elev= 30
    2842 2019.88  3083.2 2015.59  4085.6 1977.53  4487.6 1959.83  4562.6 1953.37
  4585.7 1948.66  4603.4 1938.95  4626.6 1932.22  4714.5 1928.64  4889.8 1921.97
  4955.6 1910.87  4995.8 1908.47  5055.7 1906.17  5117.1  1907.7  5173.3 1908.55
  5220.7 1916.55  5238.4 1934.74  5243.9 1934.88  5261.5  1958.7    5267  1959.2
  5284.5 1982.68  5305.4 1992.17  5350.3 2011.15  5394.2 2020.98  5463.2 2024.48
  5532.7 2021.44  5624.4 2033.59  5743.3 2055.64  5909.5 2082.18  6135.5 2095.02
#Mann= 8 ,-1 , 0
    2842     .07       0  4085.6     .12       0  4714.5     .07       0
  4995.8     .04       0  5117.1     .07       0  5173.3    .035       0
  5305.4     .12       0  5743.3     .07       0
Bank Sta=4995.8,5117.1
XS Rating Curve= 0 ,0
Exp/Cntr=0.3,0.1

Type RM Length L Ch R = 1 ,2349184 ,1369,1369,1369
BEGIN DESCRIPTION:
Guadalupe River - 230
END DESCRIPTION:
XS GIS Cut Line= 5
      1817472.79     13932249.91      1818207.02      13930895.4
      1818320.95     13930300.41      1818004.47     13929794.04
      1818169.02     13929275.05
#Sta/Elev= 30
  3043.4 2012.26  3294.9 2004.27  4213.8 1972.09  4459.1 1948.62  4516.3 1924.86
  4709.1  1923.5  4857.3 1914.39  4917.2 1910.39  4959.4  1906.1  5005.9  1907.1
  5012.1 1915.77  5026.4 1914.88  5040.8 1922.48  5052.9 1922.74  5063.1 1914.44
  5083.5 1917.64  5103.8 1907.19  5130.5 1908.54  5135.6 1921.72  5144.5 1961.47
  5164.9 1984.37  5175.1 2008.82  5219.9 2017.97  5364.4 2039.56  5641.5 2044.66
  5841.1 2059.57  6104.6 2093.71  6151.3 2105.55  6247.6 2124.39  6331.5 2125.88
#Mann= 8 ,-1 , 0
  3043.4     .07       0  3294.9     .12       0  4857.3     .07       0
  4917.2     .04       0  5012.1     .12       0  5040.8     .12       0
  5219.9     .12       0  6151.3     .07       0
Bank Sta=4917.2,5012.1
XS Rating Curve= 0 ,0
Exp/Cntr=0.3,0.1