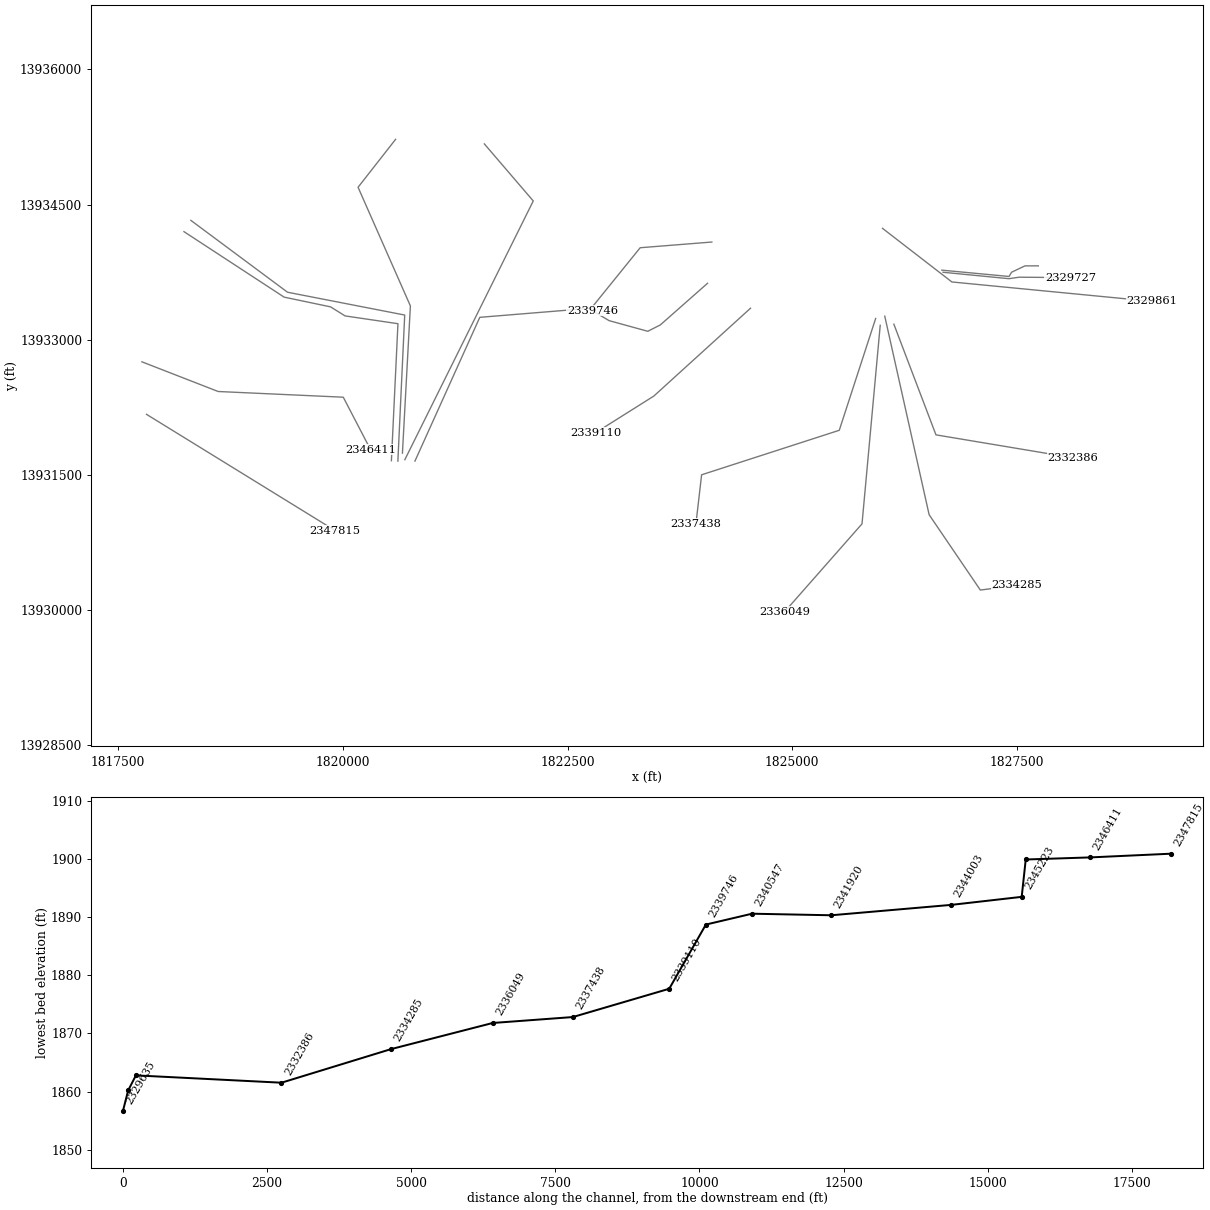
HEC-RAS study Guadalupe River.prj: Guadalupe River Base Level Engineering

--- Guadalupe River.g01 (geometry) --- (continued)

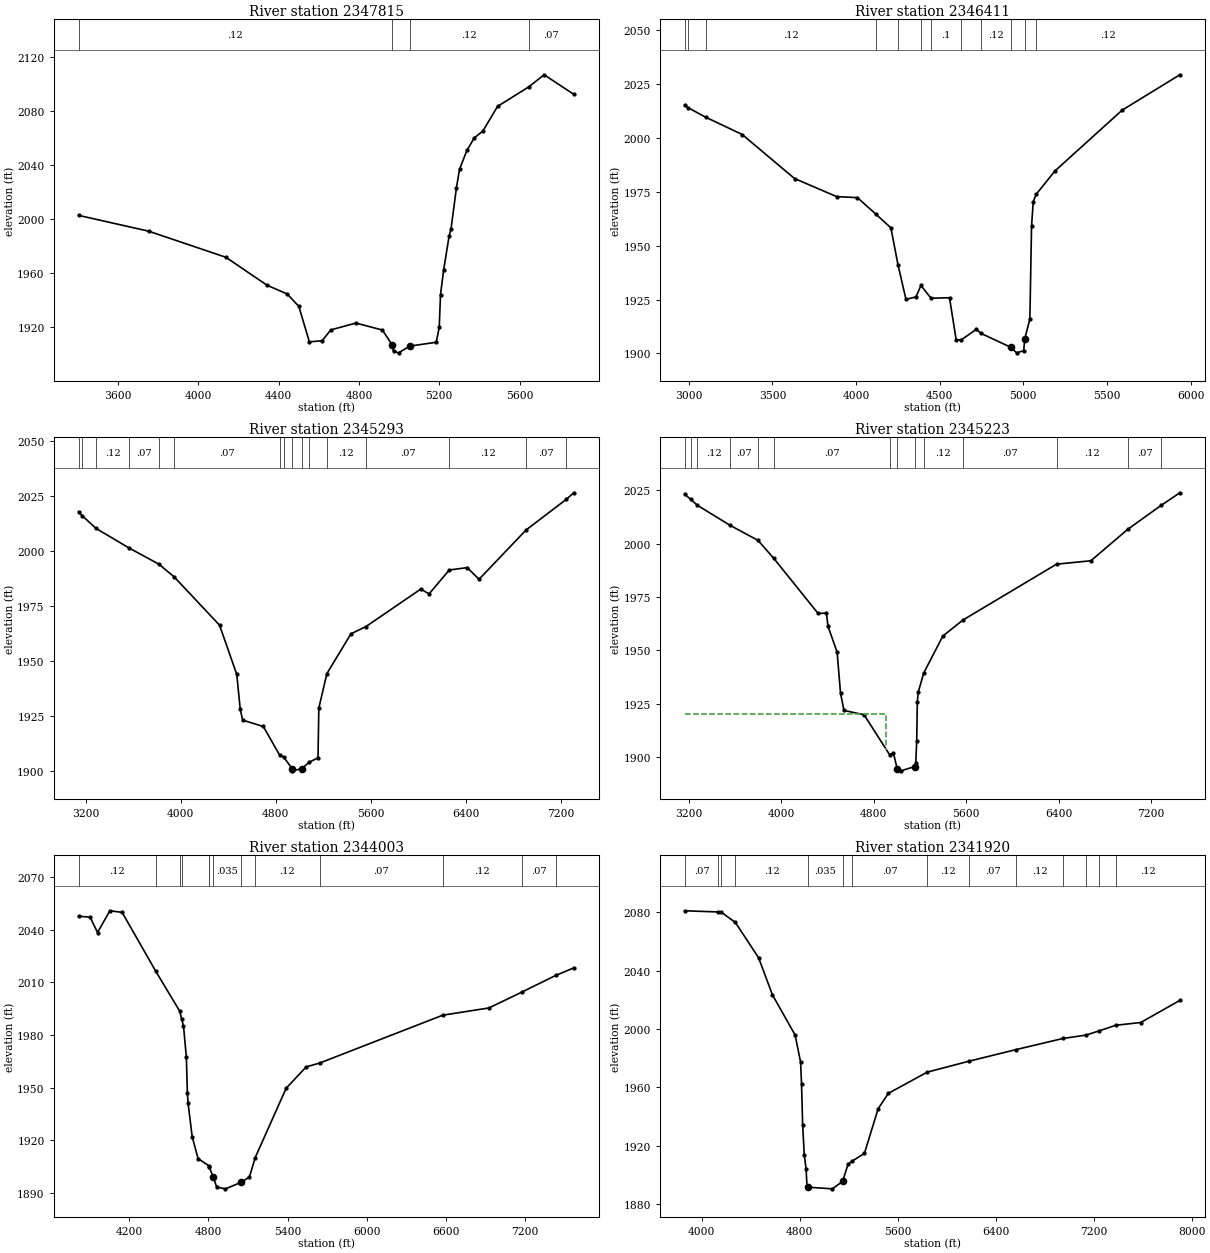
Type RM Length L Ch R = 1 ,2347815 ,1404,1404,1404
BEGIN DESCRIPTION:
Guadalupe River - 229
END DESCRIPTION:
XS GIS Cut Line= 2
      1817814.58     13932173.98      1819915.98     13930882.76
#Sta/Elev= 30
  3403.7 2002.82  3752.8 1991.11  4137.5 1971.74  4342.3 1951.05  4442.8 1944.53
  4500.8 1935.32    4553 1909.05  4616.8 1909.94    4660 1917.96  4784.9 1923.01
  4916.3 1917.87  4965.2 1906.95  4972.7 1901.94  4997.6 1900.94  5053.6 1905.95
    5185 1908.77  5199.9 1919.84  5206.3 1944.17  5221.7 1962.19  5248.9 1987.33
  5258.4 1992.59  5285.6 2023.21    5301 2036.99  5337.7 2050.92  5374.4 2060.23
    5417 2065.27  5490.4 2083.59  5645.3 2098.01  5722.4 2107.03  5870.1 2092.53
#Mann= 4 ,-1 , 0
  3403.7     .12       0  4965.2     .04       0  5053.6     .12       0
  5645.3     .07       0
Bank Sta=4965.2,5053.6
XS Rating Curve= 0 ,0
Exp/Cntr=0.3,0.1

Type RM Length L Ch R = 1 ,2346411 ,1118,1118,1118
BEGIN DESCRIPTION:
Guadalupe River - 228
END DESCRIPTION:
XS GIS Cut Line= 4
      1817763.94     13932756.31      1818612.11     13932427.17
      1820004.63     13932363.87      1820308.47     13931781.52
#Sta/Elev= 30
  2975.6 2014.95  2996.3 2013.86  3103.4 2009.39  3319.7 2001.46  3632.6 1981.05
  3884.3 1972.69  4008.4 1972.21  4118.2  1964.6  4208.6  1958.2    4251  1941.1
  4298.7 1925.07  4358.8 1926.22  4388.1  1931.5  4448.7 1925.59    4559 1925.83
    4599 1906.25  4630.4 1906.36  4719.1 1911.19  4745.2 1909.39  4924.2 1902.92
  4960.6  1900.3  5002.6  1901.3  5009.4 1906.93  5039.5 1915.97  5049.5 1958.85
  5059.5 1970.28  5077.1 1973.74  5189.6 1984.58  5590.9 2012.72  5936.2 2029.13
#Mann= 12 ,-1 , 0
  2975.6     .12       0  2996.3     .07       0  3103.4     .12       0
  4118.2     .07       0    4251      .1       0  4388.1     .07       0
  4448.7      .1       0  4630.4     .07       0  4745.2     .12       0
  4924.2    .035       0  5009.4    .035       0  5077.1     .12       0
Bank Sta=4924.2,5009.4
XS Rating Curve= 0 ,0
Exp/Cntr=0.3,0.1

Type RM Length L Ch R = 1 ,2345293 ,70,70,70
BEGIN DESCRIPTION:
Guadalupe River - 227.5
END DESCRIPTION:
XS GIS Cut Line= 6
       1818231.8     13934200.68      1819346.38     13933474.12
      1819862.94     13933366.18      1820024.76     13933265.79
      1820613.04     13933179.42      1820540.16     13931659.28
#Sta/Elev= 30
  3141.8 2017.78  3172.3 2015.96  3288.1  2010.2  3567.9 2001.24  3816.8 1993.95
  3945.6 1988.15  4327.4 1966.16  4472.3 1943.76  4501.5 1927.84    4522 1922.99
  4695.6 1920.11  4831.9 1907.15  4868.3 1906.05  4938.5 1900.94    4940 1899.94
  5019.3 1900.94    5083 1903.94  5155.4 1905.83  5162.4 1928.49  5229.8 1944.13
  5432.5 1962.25  5558.4 1965.54  6019.7 1982.59  6089.8 1980.42  6259.8 1991.29
  6410.2 1992.36  6510.3 1987.07  6905.8 2009.49  7245.2 2023.47  7306.9  2026.4
#Mann= 16 ,-1 , 0
  3141.8     .12       0  3172.3     .07       0  3288.1     .12       0
  3567.9     .07       0  3816.8     .12       0  3945.6     .07       0
  4831.9     .12       0  4868.3     .05       0  4938.5     .05       0
  5019.3     .05       0    5083    .035       0  5229.8     .12       0
  5558.4     .07       0  6259.8     .12       0  6905.8     .07       0
  7245.2     .12       0
Bank Sta=4938.5,5019.3
XS Rating Curve= 0 ,0
Exp/Cntr=0.3,0.1

Type RM Length L Ch R = 1 ,2345223 ,1220,1220,1220
BEGIN DESCRIPTION:
Guadalupe River - 227
END DESCRIPTION:
XS GIS Cut Line= 4
      1818308.32     13934326.03      1819384.33     13933528.52
      1820688.23     13933275.34      1820612.27     13931654.91
#Sta/Elev= 30
  3161.3 2023.06  3215.3 2020.64  3270.7 2017.93  3551.2 2008.63  3797.2 2001.45
  3933.2 1993.05  4317.2 1967.24  4389.4  1967.4  4402.8 1961.26  4482.1 1949.08
  4511.5 1929.92  4541.2  1921.8  4715.2  1919.8  4936.6 1901.08    4970 1901.84
  5002.1 1894.51  5034.5 1893.51  5153.3  1895.5  5163.5 1897.41  5171.7 1907.68
  5176.8 1925.55  5183.8 1930.21  5232.3 1939.35  5397.8 1956.64  5570.5 1964.11
  6382.9 1990.33  6680.2 1991.92  6999.5 2006.64    7290 2017.91  7451.1 2023.77
#Mann= 14 ,-1 , 0
  3161.3     .12       0  3215.3     .07       0  3270.7     .12       0
  3551.2     .07       0  3797.2     .12       0  3933.2     .07       0
  4936.6     .05       0  5002.1     .04       0  5153.3     .05       0
  5232.3     .12       0  5570.5     .07       0  6382.9     .12       0
  6999.5     .07       0    7290     .12       0
#XS Ineff= 2 , 0
       0 4908.43 1920.33               0
Permanent Ineff=
       F       F
Bank Sta=5002.1,5153.3
XS Rating Curve= 0 ,0
Exp/Cntr=0.3,0.1

Type RM Length L Ch R = 1 ,2344003 ,2083,2083,2083
BEGIN DESCRIPTION:
Guadalupe River - 226
END DESCRIPTION:
XS GIS Cut Line= 4
      1820586.96     13935224.87       1820169.2     13934693.17
      1820751.53     13933376.61      1820662.91     13931743.59
#Sta/Elev= 30
  3816.9 2047.89  3904.2 2047.29  3960.3 2038.53  4053.4 2050.96  4146.5 2050.06
  4400.1 2016.58  4582.7 1993.64  4597.7 1989.06  4611.4 1985.26  4633.2 1967.29
    4641 1946.63  4646.5 1940.88    4677    1922  4721.9 1909.38  4802.2 1905.38
    4805 1904.87  4838.3 1898.67  4862.7 1893.13  4929.6 1892.13  5048.7 1895.87
    5111 1898.88  5154.3  1909.9  5389.1 1949.59  5540.8 1961.78  5641.9 1963.95
  6575.6 1991.32  6925.8 1995.46  7172.3 2004.43  7433.4 2014.11  7568.1 2018.32
#Mann= 13 ,-1 , 0
  3816.9     .12       0  4400.1     .07       0  4582.7     .12       0
  4597.7     .07       0  4802.2     .12       0    4805     .05       0
  4838.3    .035       0  5048.7     .05       0  5154.3     .12       0
  5641.9     .07       0  6575.6     .12       0  7172.3     .07       0
  7433.4     .12       0
Bank Sta=4838.3,5048.7
XS Rating Curve= 0 ,0
Exp/Cntr=0.3,0.1

Type RM Length L Ch R = 1 ,2341920 ,1373,1373,1373
BEGIN DESCRIPTION:
Guadalupe River - 225
END DESCRIPTION:
XS GIS Cut Line= 3
      1821574.35     13935174.26      1822118.73     13934541.26
       1820689.7     13931670.56
#Sta/Elev= 30
  3862.2 2081.12  4136.4 2080.31  4161.4 2080.12  4275.6 2073.15  4465.2 2048.95
  4578.2 2023.52  4763.5 1995.89  4808.3 1977.35  4815.8 1962.54  4825.1 1934.43
  4838.1 1913.89  4853.1 1903.98  4860.5 1892.49  4869.9 1891.47  5067.1 1890.34
  5150.9 1895.38  5195.6 1907.19  5228.1 1909.27  5329.6  1914.7  5441.3 1945.33
  5524.8 1955.87  5841.3 1970.39  6183.9 1977.94  6568.1  1985.9  6950.6 1993.53
  7137.8 1995.81  7245.4 1998.74    7382 2002.59  7584.7 2004.46  7903.8 2019.62
#Mann= 14 ,-1 , 0
  3862.2     .07       0  4136.4     .12       0  4161.4     .07       0
  4275.6     .12       0  4869.9    .035       0  5150.9    .035       0
  5228.1     .07       0  5841.3     .12       0  6183.9     .07       0
  6568.1     .12       0  6950.6     .07       0  7137.8     .12       0
  7245.4     .07       0    7382     .12       0
Bank Sta=4869.9,5150.9
XS Rating Curve= 0 ,0
Exp/Cntr=0.3,0.1

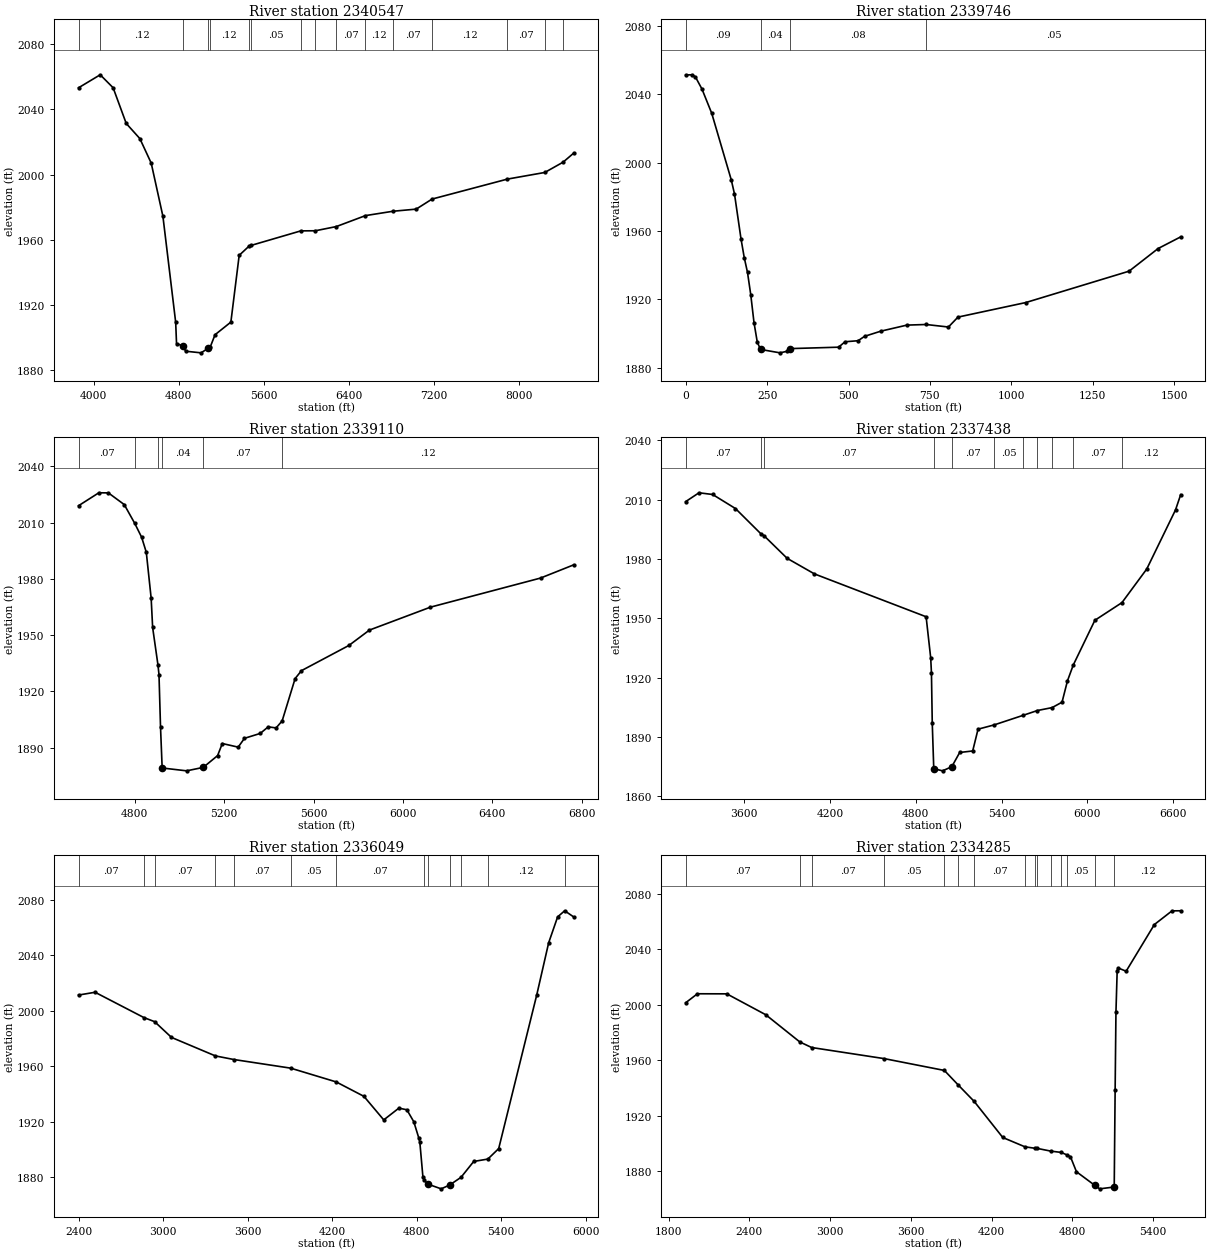
Type RM Length L Ch R = 1 ,2340547 ,801,801,801
BEGIN DESCRIPTION:
Guadalupe River - 224
END DESCRIPTION:
XS GIS Cut Line= 5
      1824106.22     13934085.53       1823308.7     13934022.23
      1822764.35     13933351.29      1821523.74     13933250.02
      1820802.18     13931654.99
#Sta/Elev= 30
  3857.6 2053.29    4061 2061.25  4182.6 2053.28  4305.9 2031.39  4434.3 2022.08
    4541 2007.07  4651.3 1974.39  4771.5 1909.34  4779.5  1896.3  4843.4 1894.77
    4865 1891.61  5010.5 1890.61  5078.3 1893.45  5095.6 1894.02  5142.3 1901.74
    5291 1909.47  5369.3 1950.45  5458.5 1955.87    5480 1956.51  5949.8 1965.46
  6086.2 1965.52  6283.5  1968.1  6558.3 1974.83    6817  1977.5  7035.3  1978.8
  7185.1 1984.98  7894.9 1997.24    8246  2001.3  8418.3 2007.61    8517  2013.1
#Mann= 16 ,-1 , 0
  3857.6     .07       0    4061     .12       0  4843.4    .035       0
  5078.3    .035       0  5095.6     .12       0  5458.5     .07       0
    5480     .05       0  5949.8     .07       0  6086.2     .05       0
  6283.5     .07       0  6558.3     .12       0    6817     .07       0
  7185.1     .12       0  7894.9     .07       0    8246     .12       0
  8418.3     .07       0
Bank Sta=4843.4,5078.3
XS Rating Curve= 0 ,0
Exp/Cntr=0.3,0.1

Type RM Length L Ch R = 1 ,2339746 ,636,636,636
XS GIS Cut Line= 5
  1824058.11781713933627.7365885 1823533.058828113933165.9724201
 1823393.380629713933095.2442151 1822962.825060413933213.2997533
 1822775.325107313933324.4107516
#Sta/Elev= 30
       0 2051.41   19.98 2051.51   29.97 2050.21   49.94 2043.15   79.91 2028.96
  139.84 1990.04  149.83 1981.74  169.81 1955.47   179.8 1944.45  189.79  1935.8
  199.78 1922.75  209.77 1906.42  219.76 1895.05  229.74 1890.73  289.68 1888.74
  309.66 1889.59  319.64 1891.21  469.48 1892.05  489.46 1895.23  529.41 1895.83
  549.39 1898.41  599.33 1901.43  679.25 1904.97  738.36 1905.33  806.86 1903.85
  836.22 1909.66 1044.29 1918.17 1361.68 1936.54 1450.84 1949.79 1520.19 1956.62
#Mann= 4 ,-1 , 0
       0     .09       0  229.74     .04       0  319.64     .08       0
  738.36     .05       0
Bank Sta=229.74,319.64
XS Rating Curve= 0 ,0
Exp/Cntr=0.3,0.1

Type RM Length L Ch R = 1 ,2339110 ,1672,1672,1672
BEGIN DESCRIPTION:
Guadalupe River - 223
END DESCRIPTION:
XS GIS Cut Line= 3
      1824536.65      13933351.3      1823460.61     13932376.53
      1822814.99     13931971.43
#Sta/Elev= 30
  4548.8    2019  4639.4 2025.88    4682 2025.82    4753 2019.59  4799.9 2009.59
  4830.7  2002.2  4851.6 1994.19  4873.3 1969.77    4880 1954.09    4904 1933.94
  4908.4 1928.98  4915.3 1900.86  4922.6 1879.21  5032.1 1877.69  5106.4 1879.53
  5170.6 1885.81  5191.6 1892.25  5262.6 1890.32  5290.9 1895.03  5361.2 1897.62
    5397 1901.13  5432.2 1900.56  5459.3 1904.29  5517.3 1926.85  5545.7 1931.08
  5757.9 1944.51  5849.9 1952.71  6122.7 1964.92  6615.2 1980.43  6762.9 1987.44
#Mann= 6 ,-1 , 0
  4548.8     .07       0  4799.9     .12       0    4904     .07       0
  4922.6     .04       0  5106.4     .07       0  5459.3     .12       0
Bank Sta=4922.6,5106.4
XS Rating Curve= 0 ,0
Exp/Cntr=0.3,0.1

Type RM Length L Ch R = 1 ,2337438 ,1389,1389,1389
BEGIN DESCRIPTION:
Guadalupe River - 222
END DESCRIPTION:
XS GIS Cut Line= 4
      1825929.18      13933237.4      1825524.07     13931996.75
       1823992.3     13931503.04      1823929.08     13930959.38
#Sta/Elev= 30
  3190.7 2008.95  3283.7  2013.4  3379.3 2012.53  3538.8 2005.42    3716  1992.7
  3737.4 1991.76  3900.1 1980.26  4091.4 1972.37  4872.1 1950.72  4904.2 1929.92
  4909.4 1922.35  4915.1  1896.9  4925.6 1873.92  4986.8 1872.82  5051.7  1874.9
    5107  1882.1  5197.9 1882.87  5235.3 1893.88  5348.8 1896.06  5548.3 1900.83
  5650.9 1903.32  5753.4 1904.79  5822.8 1907.53  5860.7 1918.32  5901.6 1926.36
  6052.5 1948.94  6241.9 1957.87  6415.3 1974.86  6616.6 2004.76  6652.5 2012.42
#Mann= 11 ,-1 , 0
  3190.7     .07       0    3716     .12       0  3737.4     .07       0
  4925.6     .04       0  5051.7     .07       0  5348.8     .05       0
  5548.3     .12       0  5650.9     .07       0  5753.4     .12       0
  5901.6     .07       0  6241.9     .12       0
Bank Sta=4925.6,5051.7
XS Rating Curve= 0 ,0
Exp/Cntr=0.3,0.1

Type RM Length L Ch R = 1 ,2336049 ,1764,1764,1764
BEGIN DESCRIPTION:
Guadalupe River - 221
END DESCRIPTION:
XS GIS Cut Line= 3
      1825979.81     13933161.44      1825777.25     13930958.69
      1824916.42     13929983.93
#Sta/Elev= 30
  2400.5 2011.48  2517.4 2013.48  2863.5 1995.26  2940.1 1992.28  3059.7 1980.94
  3371.4  1967.6  3502.2 1965.01  3905.1 1958.79  4228.6 1948.86  4425.4 1938.46
    4566 1921.49  4673.2 1929.96  4730.1 1928.79  4779.4 1920.13  4815.4 1908.22
  4822.1 1905.42  4843.9 1880.46  4854.7 1877.89    4879  1875.2  4973.6  1871.8
  5034.6 1874.61  5114.3  1880.1  5204.5 1891.54  5304.8 1893.26  5381.7 1900.81
  5651.1 2011.27  5736.4 2049.18    5800 2067.82    5850 2072.21    5913 2067.84
#Mann= 13 ,-1 , 0
  2400.5     .07       0  2863.5     .12       0  2940.1     .07       0
  3371.4     .12       0  3502.2     .07       0  3905.1     .05       0
  4228.6     .07       0  4854.7     .05       0    4879    .035       0
  5034.6    .035       0  5114.3     .07       0  5304.8     .12       0
    5850     .07       0
Bank Sta=4879,5034.6
XS Rating Curve= 0 ,0
Exp/Cntr=0.3,0.1

Type RM Length L Ch R = 1 ,2334285 ,1899,1899,1899
BEGIN DESCRIPTION:
Guadalupe River - 220
END DESCRIPTION:
XS GIS Cut Line= 4
      1826030.44     13933262.67      1826524.15     13931059.97
      1827093.82     13930224.45      1827498.88     13930275.09
#Sta/Elev= 30
  1927.4 2001.41  2014.5 2007.87  2232.5 2007.81  2522.1 1992.75  2775.5 1973.11
  2863.4 1969.13  3402.9 1961.12  3848.8 1952.62  3951.3 1942.18  4070.2 1930.31
  4282.7  1904.3  4447.5 1897.58  4523.5 1896.51  4533.5 1896.54    4640 1894.47
  4717.2 1893.54  4756.4 1891.87  4785.4 1890.44  4830.2 1879.61  4965.4 1869.87
  5002.8  1867.3  5110.6 1868.62  5117.4 1938.75  5123.5 1994.82  5132.4 2024.05
  5138.4 2026.51  5199.1 2024.12  5408.8 2057.74  5539.8 2067.61  5604.2 2067.67
#Mann= 15 ,-1 , 0
  1927.4     .07       0  2775.5     .12       0  2863.4     .07       0
  3402.9     .05       0  3848.8     .07       0  3951.3     .12       0
  4070.2     .07       0  4447.5     .12       0  4523.5     .07       0
  4533.5     .12       0    4640     .07       0  4717.2     .12       0
  4756.4     .05       0  4965.4     .04       0  5110.6     .12       0
Bank Sta=4965.4,5110.6
XS Rating Curve= 0 ,0
Exp/Cntr=0.3,0.1

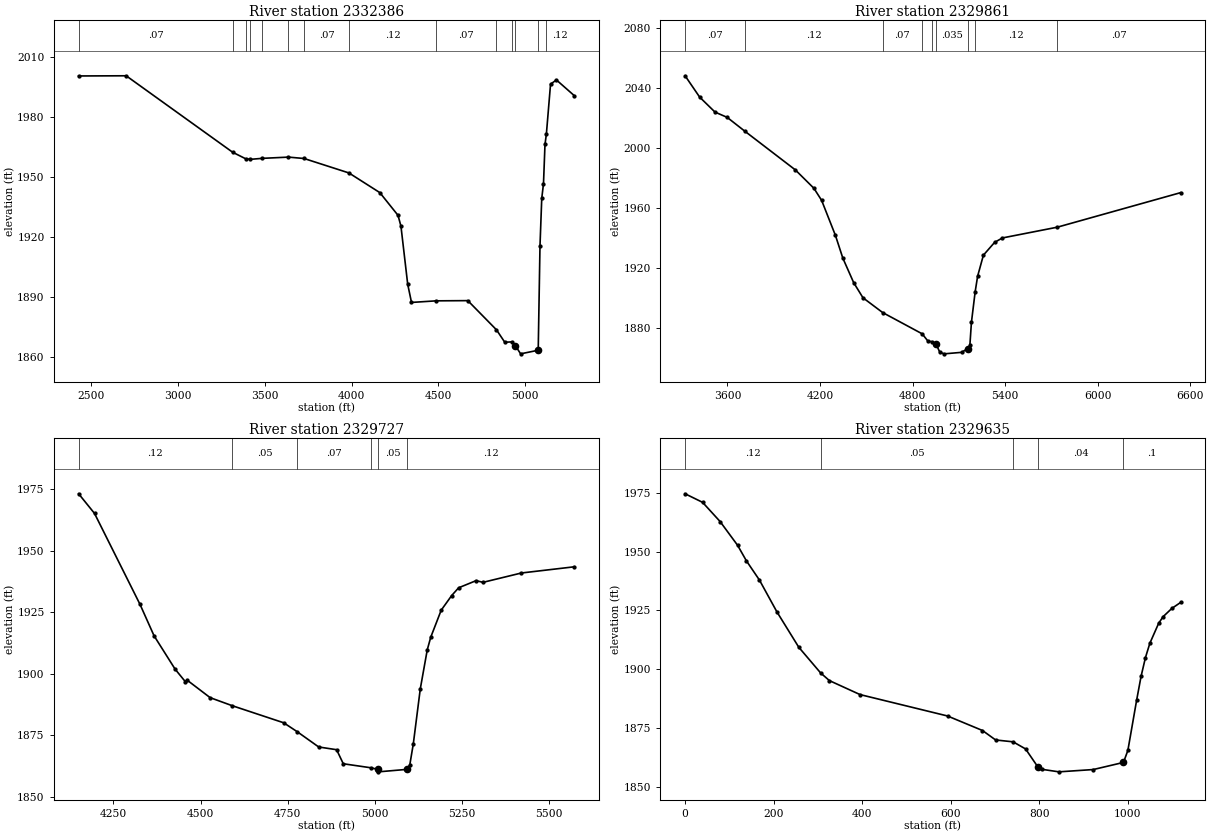
Type RM Length L Ch R = 1 ,2332386 ,2525,2525,2525
BEGIN DESCRIPTION:
Guadalupe River - 219
END DESCRIPTION:
XS GIS Cut Line= 3
      1826131.73     13933174.02      1826600.11     13931946.11
      1828119.25     13931692.92
#Sta/Elev= 30
  2427.4  2000.5  2701.2 2000.59  3314.6 1962.34  3389.1  1959.1    3417  1958.8
  3484.7 1959.29  3636.1 1959.91  3725.7 1959.22  3984.1    1952  4162.2 1942.16
    4267  1930.8  4283.9  1925.4  4322.8 1896.34  4344.7 1887.23  4487.3 1888.03
  4669.1 1888.13  4834.3 1873.52    4882 1867.31  4921.4  1867.5  4942.8 1865.65
  4973.2 1861.52  5074.6 1863.32  5084.8 1915.45  5094.9 1939.22    5105 1946.65
  5113.6 1966.23  5121.6 1971.42  5145.6 1996.41  5179.5  1998.5  5281.7  1990.7
#Mann= 14 ,-1 , 0
  2427.4     .07       0  3314.6     .12       0  3389.1     .07       0
    3417     .12       0  3484.7     .07       0  3636.1     .12       0
  3725.7     .07       0  3984.1     .12       0  4487.3     .07       0
  4834.3     .12       0  4921.4     .05       0  4942.8    .035       0
  5074.6     .12       0  5121.6     .12       0
Bank Sta=4942.8,5074.6
XS Rating Curve= 0 ,0
Exp/Cntr=0.3,0.1

Type RM Length L Ch R = 1 ,2329861 ,134,134,134
BEGIN DESCRIPTION:
Guadalupe River - 218
END DESCRIPTION:
XS GIS Cut Line= 3
      1826005.09     13934237.46      1826777.34     13933642.45
      1829005.38     13933427.25
#Sta/Elev= 30
  3325.1 2048.27  3419.5 2034.04  3519.1 2024.04  3597.9 2020.53  3711.3 2011.39
  4040.1 1985.47  4160.5  1973.2  4210.3 1965.18    4300 1941.77  4347.9 1926.63
  4418.2 1910.27  4478.5 1900.18  4606.1 1890.32  4862.3 1876.14  4900.4  1871.2
  4926.3 1870.88  4952.6 1869.26  4977.1 1863.78  5005.2 1862.78  5118.8 1863.78
  5157.1 1866.33  5171.7 1868.38  5181.7 1883.69    5206 1904.19  5221.9 1914.54
  5259.4  1928.6  5332.4 1937.17  5382.7 1940.09  5738.4 1947.26  6538.4 1970.31
#Mann= 9 ,-1 , 0
  3325.1     .07       0  3711.3     .12       0  4606.1     .07       0
  4862.3     .05       0  4926.3     .07       0  4952.6    .035       0
  5157.1     .07       0    5206     .12       0  5738.4     .07       0
Bank Sta=4952.6,5157.1
XS Rating Curve= 0 ,0
Exp/Cntr=0.3,0.1

Type RM Length L Ch R = 1 ,2329727 ,92,92,92
BEGIN DESCRIPTION:
Guadalupe River - 217.5
END DESCRIPTION:
XS GIS Cut Line= 4
      1826679.61     13933749.99      1827412.27     13933678.81
      1827524.67     13933695.22      1828096.35     13933690.96
#Sta/Elev= 30
  4150.3 1973.04  4195.9 1965.06  4326.5 1928.11  4366.7 1915.39    4427 1901.87
  4456.3 1896.79  4461.3 1897.43  4527.5  1890.3  4590.7 1887.04  4738.5  1880.1
    4778 1876.41  4838.9 1870.28  4890.3 1869.17  4909.4 1863.47    4988 1861.85
  5008.7 1861.19  5010.2 1860.19    5092 1861.19  5100.3 1863.09  5110.3 1871.56
  5130.3 1893.87  5150.3 1909.71  5160.3 1914.83  5190.3  1925.8  5220.3 1931.73
  5240.3 1934.89  5290.3 1937.78  5310.3  1937.1  5420.3 1940.89  5571.7  1943.4
#Mann= 6 ,-1 , 0
  4150.3     .12       0  4590.7     .05       0    4778     .07       0
    4988    .035       0  5008.7     .05       0    5092     .12       0
Bank Sta=5008.7,5092
XS Rating Curve= 0 ,0
Exp/Cntr=0.3,0.1

Type RM Length L Ch R = 1 ,2329635 ,1382,1382,1382
XS GIS Cut Line= 5
  1826665.67264113933773.4544729 1827413.574689113933703.3889962
 1827441.589724913933750.4545189 1827590.629453113933821.0521467
 1827739.669509313933821.0521467
#Sta/Elev= 30
       0 1974.47   39.54 1970.84   79.07 1962.71  118.61 1952.64  138.37  1946.1
  168.03 1937.89  207.56 1924.39  256.98  1909.4   306.4  1898.5  326.17 1895.27
  395.36 1889.35  593.03 1880.28  672.11 1874.12  701.76 1870.11  741.29 1869.32
  769.43 1866.31  796.82 1858.79  805.95 1857.68  844.75  1856.6  922.36 1857.57
  990.74 1860.59 1000.67 1865.71 1020.54 1887.07 1030.48 1897.09 1040.42 1905.06
 1050.35 1911.11 1070.22 1919.57 1080.16 1922.35 1100.03 1925.88  1119.9 1928.41
#Mann= 5 ,-1 , 0
       0     .12       0   306.4     .05       0  741.29     .12       0
  796.82     .04       0  990.74      .1       0
Bank Sta=796.82,990.74
XS Rating Curve= 0 ,0
Exp/Cntr=0.3,0.1