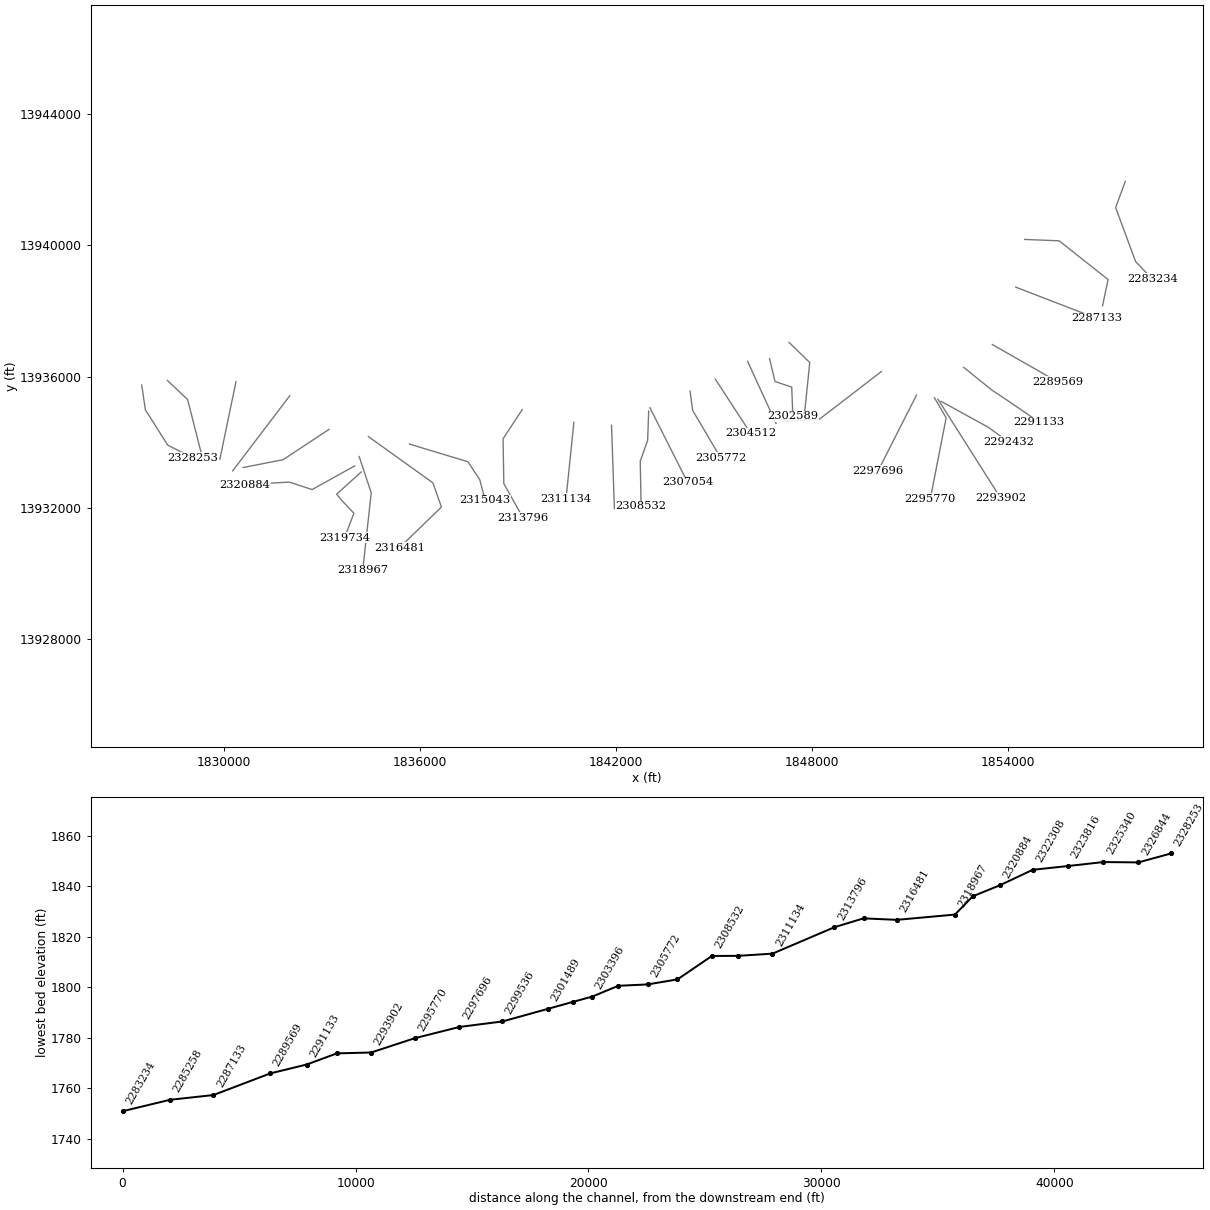
HEC-RAS study Guadalupe River.prj: Guadalupe River Base Level Engineering

--- Guadalupe River.g01 (geometry) --- (continued)

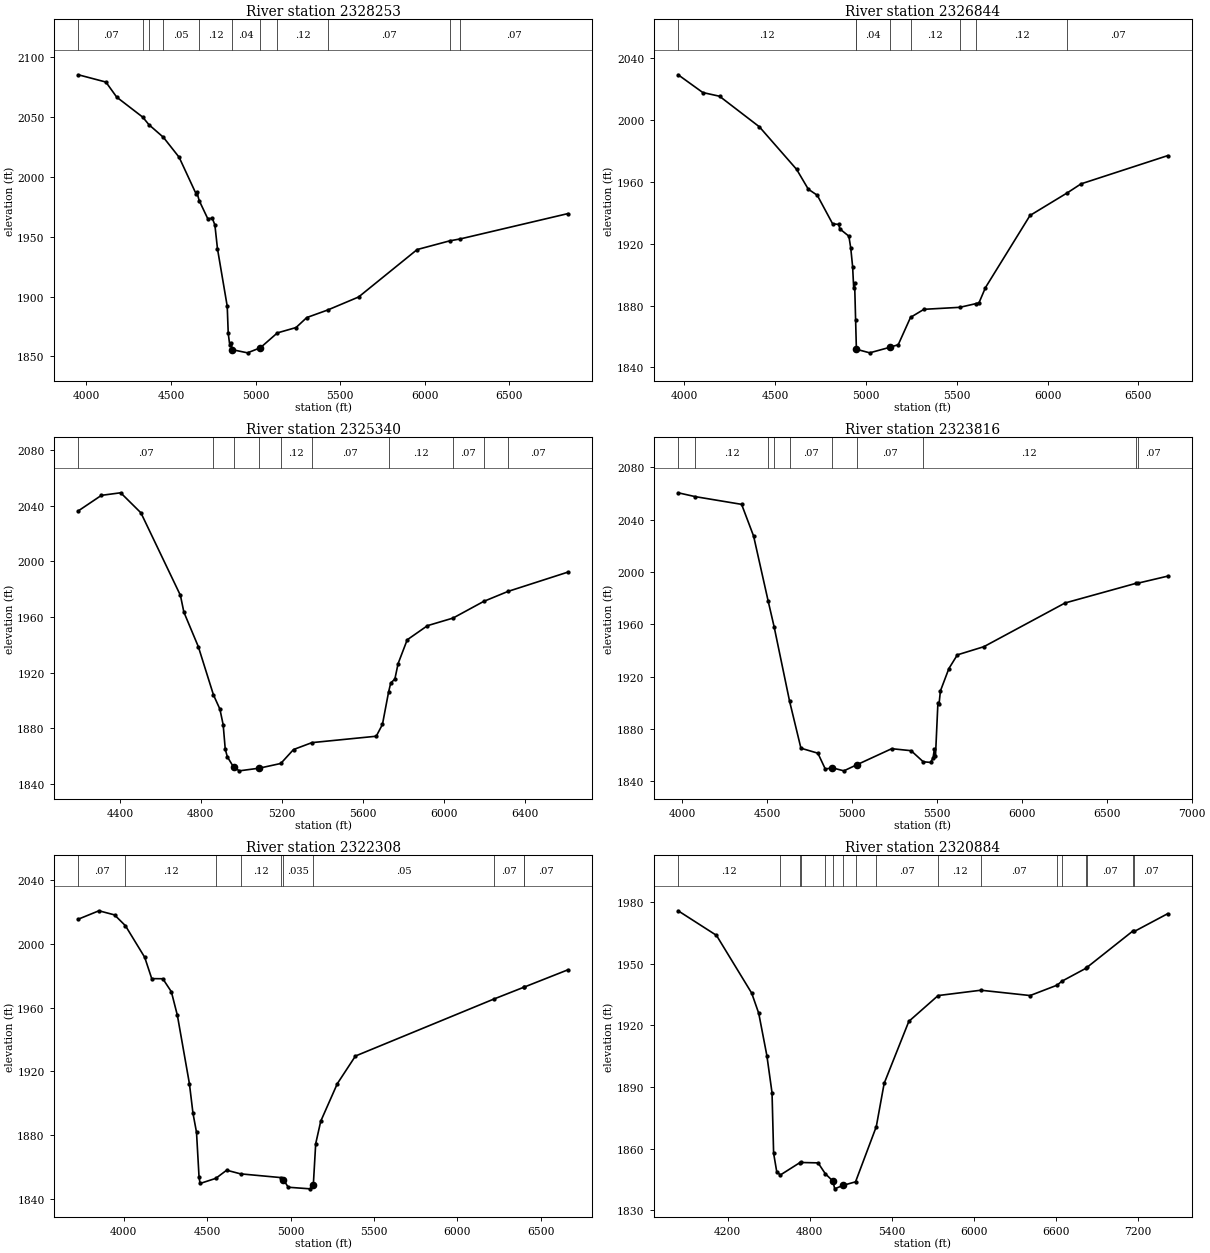
Type RM Length L Ch R = 1 ,2328253 ,1409,1409,1409
BEGIN DESCRIPTION:
Guadalupe River - 217
END DESCRIPTION:
XS GIS Cut Line= 4
      1827486.26     13935743.85      1827600.19     13934984.34
      1828283.79      13933908.3      1829043.31     13933528.54
#Sta/Elev= 30
  3952.9  2085.4  4115.8 2079.32  4179.8  2066.7  4333.6 2049.97  4370.1 2043.67
  4455.6 2033.13  4548.3 2016.49  4648.3 1985.99  4653.4 1987.07    4667 1980.26
  4717.4 1965.18  4744.5 1965.44  4759.7 1959.88    4775    1940  4832.6 1891.98
  4838.6  1869.3  4847.8 1859.17  4853.7 1861.58  4862.3 1855.66  4952.4 1853.01
  5028.2 1857.24  5128.8 1869.67  5239.1 1874.14  5302.6  1882.5  5426.3 1888.81
  5608.7 1899.68  5954.8 1939.33  6146.7 1946.59  6210.6 1948.25  6844.9 1969.36
#Mann= 11 ,-1 , 0
  3952.9     .07       0  4333.6     .05       0  4370.1     .07       0
  4455.6     .05       0    4667     .12       0  4862.3     .04       0
  5028.2     .05       0  5128.8     .12       0  5426.3     .07       0
  6146.7     .12       0  6210.6     .07       0
Bank Sta=4862.3,5028.2
XS Rating Curve= 0 ,0
Exp/Cntr=0.3,0.1

Type RM Length L Ch R = 1 ,2326844 ,1504,1504,1504
BEGIN DESCRIPTION:
Guadalupe River - 216
END DESCRIPTION:
XS GIS Cut Line= 3
      1828271.13     13935883.14      1828891.43     13935300.82
      1829347.16     13933515.89
#Sta/Elev= 30
  3967.7 2028.93  4103.5 2017.46  4195.4 2015.08  4414.7 1995.34  4619.8 1967.83
  4683.8 1955.08  4733.1 1951.17  4817.5 1932.76  4851.7 1932.31  4856.9 1929.48
  4907.1 1924.75  4917.4 1917.02  4927.7    1905  4933.4 1891.45  4938.6 1894.77
  4944.1 1870.63  4948.4 1851.76  5021.7 1849.45  5132.5 1853.03  5178.6  1854.7
  5246.2 1872.33  5319.9 1877.54  5517.4 1878.83  5608.9 1881.29  5622.8 1881.72
  5658.5 1891.57  5903.6 1938.12  6109.5 1952.78  6184.4 1958.52  6660.7 1976.73
#Mann= 8 ,-1 , 0
  3967.7     .12       0  4944.1     .07       0  4948.4     .04       0
  5132.5     .07       0  5246.2     .12       0  5517.4     .07       0
  5608.9     .12       0  6109.5     .07       0
Bank Sta=4948.4,5132.5
XS Rating Curve= 0 ,0
Exp/Cntr=0.3,0.1

Type RM Length L Ch R = 1 ,2325340 ,1524,1524,1524
BEGIN DESCRIPTION:
Guadalupe River - 215
END DESCRIPTION:
XS GIS Cut Line= 2
      1830372.57     13935845.21      1829879.07     13933478.92
#Sta/Elev= 30
  4194.9 2036.24    4309 2047.39    4404 2049.23    4504 2034.83    4699 1975.59
  4716.1 1963.54  4787.6 1938.69  4862.3 1904.08    4894  1893.9  4910.2 1882.65
  4920.4 1865.18  4930.6 1859.71  4961.2 1852.37  4990.1 1849.59    5089 1851.52
  5194.7 1854.88  5257.5 1864.88  5348.6 1869.85  5666.1 1874.44  5696.7 1882.92
    5727 1906.19  5737.6 1912.64    5758  1915.5  5774.1 1926.61    5819 1943.68
  5919.1 1953.82  6045.5 1959.29  6196.7 1971.24  6316.3 1978.39  6612.1 1992.25
#Mann= 10 ,-1 , 0
  4194.9     .07       0  4862.3     .12       0  4961.2     .04       0
    5089     .12       0  5194.7     .12       0  5348.6     .07       0
    5727     .12       0  6045.5     .07       0  6196.7     .05       0
  6316.3     .07       0
Bank Sta=4961.2,5089
XS Rating Curve= 0 ,0
Exp/Cntr=0.3,0.1

Type RM Length L Ch R = 1 ,2323816 ,1508,1508,1508
BEGIN DESCRIPTION:
Guadalupe River - 214
END DESCRIPTION:
XS GIS Cut Line= 2
      1832018.28     13935414.77      1830271.27     13933123.39
#Sta/Elev= 30
  3977.1  2060.6  4077.5 2057.66  4350.7 2051.75  4421.4 2027.46  4507.6 1977.49
  4541.9 1958.28  4633.4 1901.07  4699.9 1865.32  4799.7 1861.49  4843.3  1849.4
  4884.9  1850.3  4952.7 1848.01  5028.3 1852.61  5234.3 1864.94  5348.5 1863.41
  5419.9 1854.94  5462.8 1854.46  5477.3 1857.66  5485.6 1864.74  5491.9 1859.01
  5506.4  1900.2  5512.7 1898.78  5520.9 1909.06  5570.8  1926.2  5620.7 1936.68
  5776.7 1942.92  6254.8 1976.35    6670 1991.29  6681.5 1991.43  6858.5 1996.85
#Mann= 10 ,-1 , 0
  3977.1     .07       0  4077.5     .12       0  4507.6     .07       0
  4541.9     .12       0  4633.4     .07       0  4884.9    .035       0
  5028.3     .07       0  5419.9     .12       0    6670     .05       0
  6681.5     .07       0
Bank Sta=4884.9,5028.3
XS Rating Curve= 0 ,0
Exp/Cntr=0.3,0.1

Type RM Length L Ch R = 1 ,2322308 ,1424,1424,1424
BEGIN DESCRIPTION:
Guadalupe River - 213
END DESCRIPTION:
XS GIS Cut Line= 3
      1833220.88     13934389.34      1831815.72     13933465.23
      1830588.84     13933224.91
#Sta/Elev= 30
  3729.1 2015.34  3852.6 2020.59  3945.9 2018.01  4011.2 2011.24  4126.7 1991.46
  4168.8 1978.12  4235.2 1978.04  4286.4 1969.89  4322.5 1955.06  4394.4 1912.41
  4415.9  1893.8    4437 1881.91  4452.1 1854.04  4458.1 1849.87  4552.5 1853.08
  4617.7 1858.19  4700.6  1855.9  4940.4 1853.58    4957 1852.35  4986.5 1847.52
  5117.4 1846.52  5136.5 1848.63  5150.9 1874.77  5181.1 1888.85  5280.5 1912.37
  5388.9 1929.66    6220 1965.41  6399.1 1972.79  6400.7 1972.85  6661.1 1983.61
#Mann= 10 ,-1 , 0
  3729.1     .07       0  4011.2     .12       0  4552.5     .07       0
  4700.6     .12       0  4940.4     .05       0    4957    .035       0
  5136.5     .05       0    6220     .07       0  6399.1     .05       0
  6400.7     .07       0
Bank Sta=4957,5136.5
XS Rating Curve= 0 ,0
Exp/Cntr=0.3,0.1

Type RM Length L Ch R = 1 ,2320884 ,1150,1150,1150
BEGIN DESCRIPTION:
Guadalupe River - 212
END DESCRIPTION:
XS GIS Cut Line= 4
      1834005.76     13933275.33      1832701.87     13932553.76
      1832005.61     13932781.63      1830651.07     13932705.67
#Sta/Elev= 30
  3837.3 1975.83  4117.5 1963.86  4375.3 1935.69  4426.7 1925.87  4486.2 1905.26
  4523.9 1887.16  4535.5 1857.69  4558.2 1848.74  4584.4 1847.08  4727.8 1853.13
  4733.7 1853.19  4860.7    1853  4913.3 1847.73  4969.7 1844.07  4982.1 1840.35
  5045.1 1842.09  5134.6 1843.76  5286.3 1870.66  5343.8 1891.72  5524.2 1921.94
  5738.3 1934.52  6051.1 1937.12  6411.3 1934.53  6609.4 1939.61    6642 1941.45
  6819.9 1947.83  6826.1  1948.2  7164.4 1966.07  7174.1 1965.79  7416.8  1974.4
#Mann= 17 ,-1 , 0
  3837.3     .12       0  4584.4     .07       0  4727.8     .12       0
  4733.7     .07       0  4913.3     .12       0  4969.7     .04       0
  5045.1     .12       0  5134.6     .12       0  5286.3     .07       0
  5738.3     .12       0  6051.1     .07       0  6609.4     .12       0
    6642     .07       0  6819.9     .12       0  6826.1     .07       0
  7164.4     .12       0  7174.1     .07       0
Bank Sta=4969.7,5045.1
XS Rating Curve= 0 ,0
Exp/Cntr=0.3,0.1

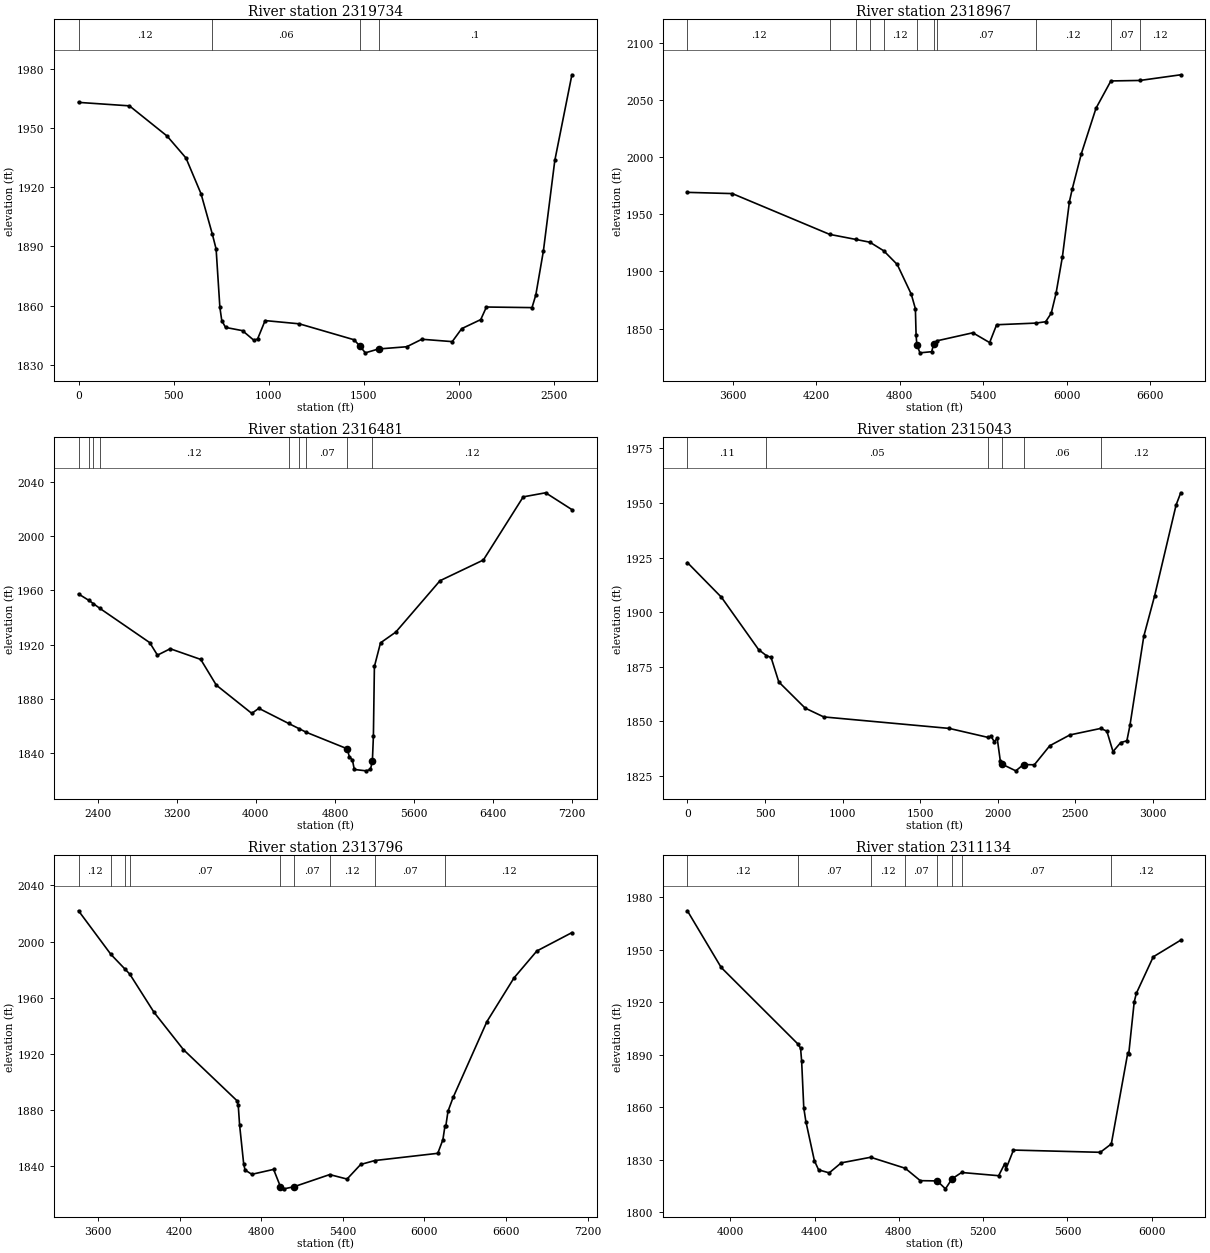
Type RM Length L Ch R = 1 ,2319734 ,767,767,767
XS GIS Cut Line= 5
  1834204.48367913933090.1251309 1833453.615430513932413.0418394
  1833592.05806713932242.2298451 1833981.466408913931833.3510696
  1833695.90037913931086.9857645
#Sta/Elev= 30
       0 1963.08  267.63 1961.32  465.88 1945.99     565 1934.88   644.3 1916.72
  703.78 1896.24   723.6 1888.71  743.43 1859.06  753.34 1852.42  773.16 1848.94
  862.38 1847.29  921.85 1842.44  941.68 1843.06  981.33  1852.4 1160.97 1850.76
 1448.86 1842.68 1478.58 1839.59  1508.3 1836.04 1577.64    1838 1726.23 1839.13
 1805.56 1842.93 1965.39 1841.73 2015.33 1848.32 2115.23  1852.9 2145.19 1859.28
 2384.93 1858.98 2404.91 1865.38 2444.87 1887.74  2504.8  1933.6 2594.71 1977.08
#Mann= 4 ,-1 , 0
       0     .12       0  703.78     .06       0 1478.58     .04       0
 1577.64      .1       0
Bank Sta=1478.58,1577.64
XS Rating Curve= 0 ,0
Exp/Cntr=0.3,0.1

Type RM Length L Ch R = 1 ,2318967 ,2486,2486,2486
BEGIN DESCRIPTION:
Guadalupe River - 211
END DESCRIPTION:
XS GIS Cut Line= 3
      1834143.26     13933561.53      1834512.18     13932454.75
      1834251.81     13930089.69
#Sta/Elev= 30
    3274 1969.07  3597.1    1968  4296.4 1932.36  4486.5 1927.89  4585.8 1925.49
  4685.1 1918.01  4782.4 1906.02  4883.1 1880.09  4912.8 1867.35  4917.9 1844.04
  4923.3 1835.95  4945.5  1828.8  5029.6  1829.8    5044 1836.15  5065.6 1839.24
  5325.7 1846.33  5446.4 1837.76  5496.7 1853.36  5777.5 1854.79  5848.9 1855.98
  5889.1 1863.39  5923.5 1880.67  5969.6 1912.85  6019.9 1960.98    6040 1971.92
  6105.4 2002.85    6211 2042.62  6317.8 2066.46  6527.3 2066.89    6820 2071.85
#Mann= 11 ,-1 , 0
    3274     .12       0  4296.4     .07       0  4486.5     .12       0
  4585.8     .07       0  4685.1     .12       0  4923.3     .04       0
    5044     .12       0  5065.6     .07       0  5777.5     .12       0
  6317.8     .07       0  6527.3     .12       0
Bank Sta=4923.3,5044
XS Rating Curve= 0 ,0
Exp/Cntr=0.3,0.1

Type RM Length L Ch R = 1 ,2316481 ,1438,1438,1438
BEGIN DESCRIPTION:
Guadalupe River - 210
END DESCRIPTION:
XS GIS Cut Line= 4
      1834425.39     13934169.15       1836400.2     13932758.57
      1836660.62     13932020.72      1835380.25     13930783.75
#Sta/Elev= 30
  2206.5 1957.36  2313.1 1952.53  2355.7 1950.26  2420.9 1946.79  2926.3 1921.43
  3004.8 1912.16    3134 1916.89  3442.4 1909.01  3599.7 1890.04  3958.6 1869.15
  4029.8  1872.9  4331.3 1861.72  4435.5 1857.92  4510.3 1855.19  4923.5 1843.02
  4944.7 1837.27  4976.5 1834.73  4995.6 1827.72    5116 1826.72  5158.6 1827.72
  5178.4 1833.99  5188.6  1852.1  5198.8 1903.79  5260.6 1921.25  5414.9 1929.18
  5862.3 1967.14  6300.7 1982.43  6703.8 2029.07  6930.2 2032.09  7196.1 2019.67
#Mann= 9 ,-1 , 0
  2206.5     .07       0  2313.1     .08       0  2355.7     .07       0
  2420.9     .12       0  4331.3     .05       0  4435.5     .12       0
  4510.3     .07       0  4923.5     .04       0  5178.4     .12       0
Bank Sta=4923.5,5178.4
XS Rating Curve= 0 ,0
Exp/Cntr=0.3,0.1

Type RM Length L Ch R = 1 ,2315043 ,1247,1247,1247
XS GIS Cut Line= 4
  1835681.78026513933941.2313683 1837469.974523713933403.0369066
 1837834.558112113932856.1620161 1837999.4885566 13932222.481525
#Sta/Elev= 30
       0 1922.69   219.7 1906.78  459.37 1882.79   509.3 1880.06  539.26 1879.25
  589.19    1868  758.96 1856.03  878.79 1851.99 1687.68 1846.73 1937.14 1842.62
 1957.06 1843.12 1976.97 1840.72 1996.89 1842.12 2016.81 1831.75 2026.77 1830.39
 2116.39  1827.3 2166.18 1830.19 2235.89 1830.06 2335.48  1838.8 2464.94 1843.74
 2663.58 1846.72 2703.27 1845.48 2742.95 1836.11 2792.56 1840.24 2832.24 1841.06
 2852.08  1848.1 2941.37 1888.93 3010.82 1907.37 3149.71  1949.1 3179.48 1954.64
#Mann= 6 ,-1 , 0
       0     .11       0   509.3     .05       0 1937.14     .12       0
 2026.77     .04       0 2166.18     .06       0 2663.58     .12       0
Bank Sta=2026.77,2166.18
XS Rating Curve= 0 ,0
Exp/Cntr=0.3,0.1

Type RM Length L Ch R = 1 ,2313796 ,2662,2662,2662
BEGIN DESCRIPTION:
Guadalupe River - 209
END DESCRIPTION:
XS GIS Cut Line= 4
      1839134.59     13934993.83      1838548.64     13934104.06
      1838570.34     13932736.87      1839156.28     13931695.19
#Sta/Elev= 30
  3456.4 2021.92  3694.4 1990.86  3798.7 1980.31  3833.1 1976.81    4011 1949.66
  4227.8 1922.99  4620.8 1886.68  4630.8 1883.43  4640.8 1869.33  4670.8 1841.64
  4680.8  1837.2  4730.9 1834.16  4890.9 1837.66  4940.9 1825.41  4967.2 1823.81
  5040.9 1825.31  5303.4 1833.97  5430.9 1830.78    5531 1841.17  5635.5 1843.98
    6098 1849.12  6135.6 1858.77  6151.1 1868.66  6157.3 1868.64  6173.2 1879.08
  6210.8  1888.9  6459.4 1942.97  6658.9 1974.13  6826.5 1993.27  7084.3 2006.36
#Mann= 9 ,-1 , 0
  3456.4     .12       0  3694.4     .07       0  3798.7     .12       0
  3833.1     .07       0  4940.9     .04       0  5040.9     .07       0
  5303.4     .12       0  5635.5     .07       0  6151.1     .12       0
Bank Sta=4940.9,5040.9
XS Rating Curve= 0 ,0
Exp/Cntr=0.3,0.1

Type RM Length L Ch R = 1 ,2311134 ,1473,1473,1473
BEGIN DESCRIPTION:
Guadalupe River - 208
END DESCRIPTION:
XS GIS Cut Line= 2
      1840715.18     13934604.55      1840474.65     13932275.23
#Sta/Elev= 30
  3796.3 1972.19  3956.7 1939.82  4320.3 1896.16  4333.6 1893.69  4338.7  1886.2
  4348.8 1859.56  4358.8 1851.77    4399 1829.48  4419.1 1824.19  4469.4 1822.46
  4526.5 1828.18  4666.2 1831.38  4830.2  1825.1  4901.7 1818.02  4982.1 1817.86
  5021.3 1813.34  5052.5 1819.09  5098.1 1822.68  5273.7 1820.84  5302.9 1827.77
    5308 1824.57    5344 1835.49  5756.2 1834.21  5808.5    1839  5886.6 1891.01
  5891.2 1890.53  5917.1 1920.09  5927.1 1924.99  6007.5 1945.88    6138 1955.42
#Mann= 8 ,-1 , 0
  3796.3     .12       0  4320.3     .07       0  4666.2     .12       0
  4830.2     .07       0  4982.1     .04       0  5052.5     .07       0
  5098.1     .07       0  5808.5     .12       0
Bank Sta=4982.1,5052.5
XS Rating Curve= 0 ,0
Exp/Cntr=0.3,0.1

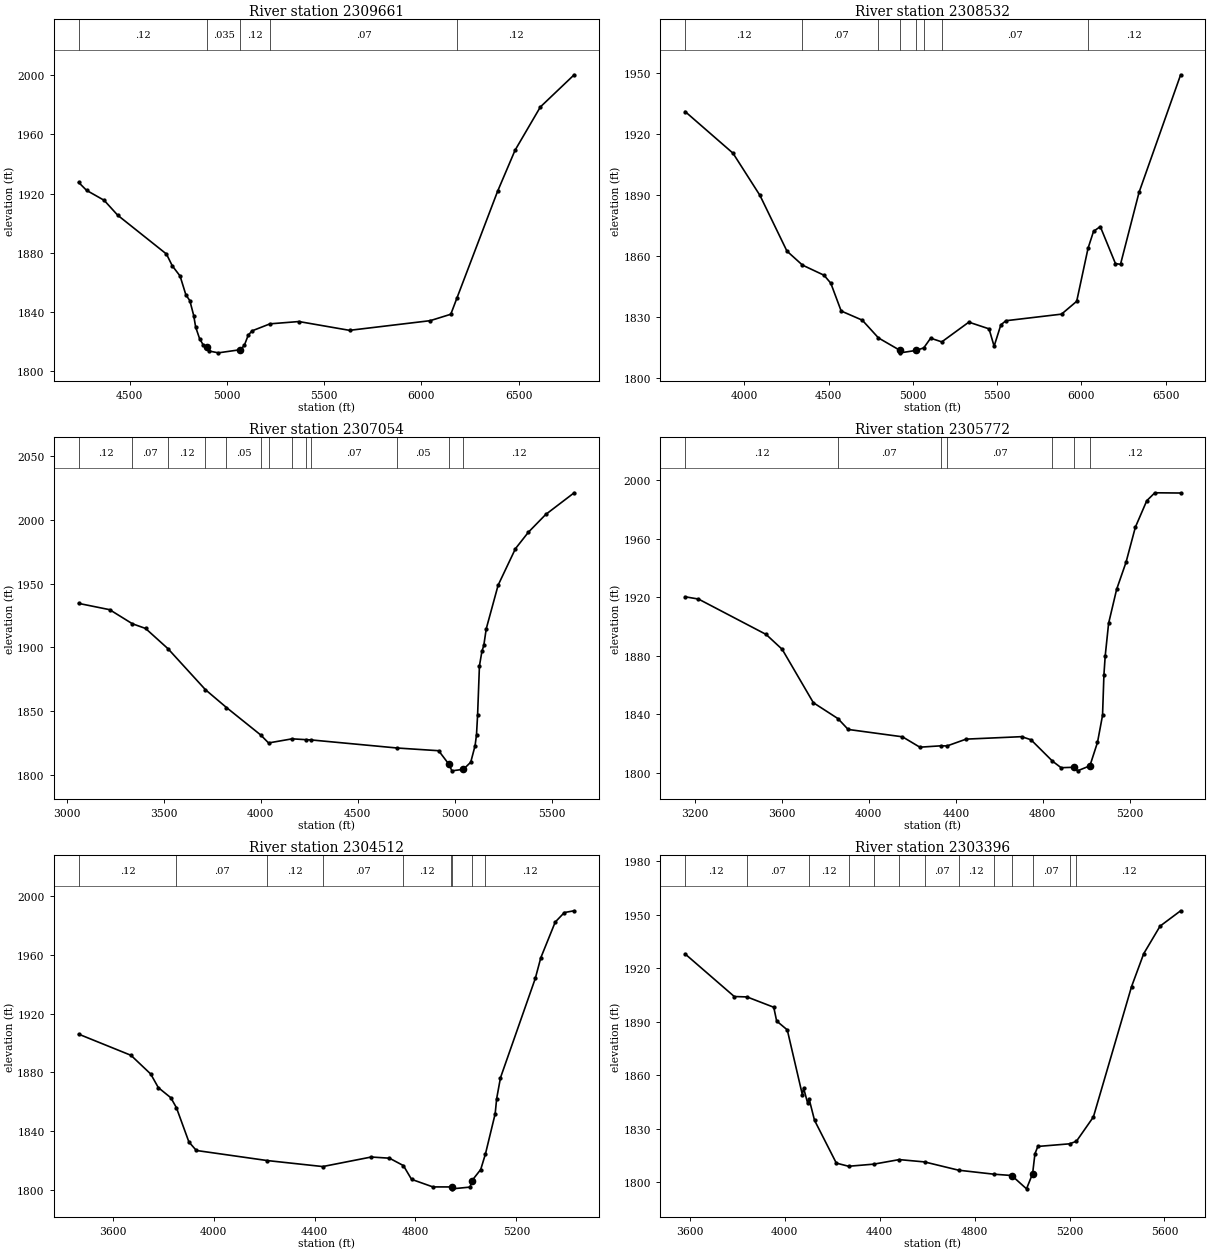
Type RM Length L Ch R = 1 ,2309661 ,1129,1129,1129
BEGIN DESCRIPTION:
Guadalupe River - 207
END DESCRIPTION:
XS GIS Cut Line= 2
      1841867.18      13934515.9      1841955.79     13931971.44
#Sta/Elev= 30
  4238.5 1927.54  4279.4 1922.16  4369.5 1915.46  4439.5 1905.35  4689.7 1879.18
  4719.7 1871.22  4759.7 1864.33  4789.7 1851.54  4809.7 1847.76  4829.8 1837.63
  4839.8 1829.82  4859.8 1822.11  4879.8 1817.52  4899.8 1816.45  4909.8 1813.67
  4956.3 1812.47  5069.9  1814.6  5089.9 1817.55  5109.9 1824.42  5129.9 1827.33
  5221.8 1832.05  5370.1  1833.6  5630.2 1827.66  6044.5 1834.18  6150.6 1838.52
  6182.7 1849.66  6390.7 1921.42  6480.8 1949.26  6610.8 1978.48  6784.5  2000.2
#Mann= 5 ,-1 , 0
  4238.5     .12       0  4899.8    .035       0  5069.9     .12       0
  5221.8     .07       0  6182.7     .12       0
Bank Sta=4899.8,5069.9
XS Rating Curve= 0 ,0
Exp/Cntr=0.3,0.1

Type RM Length L Ch R = 1 ,2308532 ,1478,1478,1478
BEGIN DESCRIPTION:
Guadalupe River - 206
END DESCRIPTION:
XS GIS Cut Line= 4
      1843004.92     13934949.04      1842972.98     13934052.35
      1842746.41     13933417.81      1842772.81     13932048.19
#Sta/Elev= 30
  3648.1 1931.15  3932.3 1910.65  4092.4 1889.87  4252.5 1862.48  4344.6 1855.59
  4472.7  1850.6  4512.7  1846.7  4574.4    1833  4699.7 1828.49  4795.8 1819.75
  4923.6 1813.62  4925.1 1812.42  5019.6 1813.62  5064.6 1814.87  5105.3 1819.63
  5171.5 1817.81    5332 1827.52    5452 1824.22    5482 1815.67    5522 1826.18
    5552 1828.22  5882.1 1831.46  5972.1 1837.77  6039.5 1863.87  6072.1 1872.19
  6112.1 1874.54  6202.1 1856.34  6232.1 1855.96  6342.1 1891.36    6589 1949.23
#Mann= 8 ,-1 , 0
  3648.1     .12       0  4344.6     .07       0  4795.8     .12       0
  4923.6     .05       0  5019.6     .12       0  5064.6     .12       0
  5171.5     .07       0  6039.5     .12       0
Bank Sta=4923.6,5019.6
XS Rating Curve= 0 ,0
Exp/Cntr=0.3,0.1

Type RM Length L Ch R = 1 ,2307054 ,1282,1282,1282
BEGIN DESCRIPTION:
Guadalupe River - 205
END DESCRIPTION:
XS GIS Cut Line= 2
       1843044.5     13935047.61      1844196.21     13932769.49
#Sta/Elev= 30
  3062.4 1934.44  3222.2 1929.51  3339.3 1918.47  3407.1  1914.8    3523 1898.87
  3715.5 1866.78  3823.9  1852.8  3999.9 1831.31  4040.8 1825.01  4162.2 1828.24
  4233.4 1827.58  4261.3 1827.36  4704.1 1821.03    4917 1818.92  4970.2 1808.22
  4985.2 1803.14  5044.5 1804.34  5082.3 1809.91  5104.7 1822.94    5112  1831.5
  5117.6 1846.93  5127.1 1885.45  5139.9 1896.83  5149.5 1901.46  5162.2 1914.57
  5223.4 1948.74  5312.6 1977.36  5379.4 1990.28  5468.6 2004.18  5615.1 2021.18
#Mann= 13 ,-1 , 0
  3062.4     .12       0  3339.3     .07       0    3523     .12       0
  3715.5     .07       0  3823.9     .05       0  3999.9     .07       0
  4040.8     .05       0  4162.2     .07       0  4233.4     .05       0
  4261.3     .07       0  4704.1     .05       0  4970.2     .04       0
  5044.5     .12       0
Bank Sta=4970.2,5044.5
XS Rating Curve= 0 ,0
Exp/Cntr=0.3,0.1

Type RM Length L Ch R = 1 ,2305772 ,1260,1260,1260
BEGIN DESCRIPTION:
Guadalupe River - 204
END DESCRIPTION:
XS GIS Cut Line= 3
      1844272.43     13935554.01      1844348.39     13934971.68
       1845209.2      13933515.9
#Sta/Elev= 30
    3155 1920.23  3216.5 1918.68  3527.5 1894.47  3601.4  1884.3  3744.8 1847.76
  3857.9 1836.88  3904.7 1829.48  4154.4 1824.44  4234.4 1817.34  4330.2 1818.27
  4359.5  1818.2    4447 1822.85  4702.5 1824.54  4745.4 1822.42  4844.3 1807.78
  4883.8 1803.31  4942.4 1803.59  4959.4 1801.16  5016.3 1804.61  5051.2 1820.64
  5074.4 1839.12  5080.8 1866.93  5086.6 1879.66  5102.3 1902.07  5139.3 1925.37
  5182.2 1943.73  5225.4 1967.87  5277.8 1985.96  5314.9 1991.38  5433.5 1991.21
#Mann= 7 ,-1 , 0
    3155     .12       0  3857.9     .07       0  4330.2     .12       0
  4359.5     .07       0  4844.3     .12       0  4942.4     .04       0
  5016.3     .12       0
Bank Sta=4942.4,5016.3
XS Rating Curve= 0 ,0
Exp/Cntr=0.3,0.1

Type RM Length L Ch R = 1 ,2304512 ,1116,1116,1116
BEGIN DESCRIPTION:
Guadalupe River - 203
END DESCRIPTION:
XS GIS Cut Line= 2
      1845044.68     13935921.08      1846120.35     13934275.93
#Sta/Elev= 30
  3463.8 1906.01  3671.4 1891.59  3749.7 1878.85    3780 1869.56  3829.5 1862.68
  3851.6 1855.94  3901.2 1832.55  3930.7 1826.75  4211.7 1819.89    4432 1815.79
  4624.4 1822.29  4696.8 1821.49  4752.1 1816.44  4784.3 1807.09    4869 1801.92
  4940.2 1801.91    4944 1801.81  4945.5 1800.61    5017 1801.81  5022.5 1805.87
  5058.7 1813.78  5077.6 1824.48    5116 1851.74    5122 1862.14  5137.1 1876.31
  5275.2 1943.99    5297 1958.04  5354.3 1982.39  5390.5 1988.88  5429.4 1990.07
#Mann= 9 ,-1 , 0
  3463.8     .12       0  3851.6     .07       0  4211.7     .12       0
    4432     .07       0  4752.1     .12       0  4940.2    .035       0
    4944     .04       0  5022.5    .035       0  5077.6     .12       0
Bank Sta=4944,5022.5
XS Rating Curve= 0 ,0
Exp/Cntr=0.3,0.1

Type RM Length L Ch R = 1 ,2303396 ,807,807,807
BEGIN DESCRIPTION:
Guadalupe River - 202
END DESCRIPTION:
XS GIS Cut Line= 2
      1846032.06     13936465.49      1846904.78     13934568.29
#Sta/Elev= 30
    3580 1928.11  3787.3 1904.21  3840.9 1903.99  3953.6  1898.2  3965.8 1890.48
  4010.6  1885.5    4074 1849.23  4079.5 1852.75  4096.9 1844.21  4102.3  1846.9
  4125.4 1834.79  4217.3 1810.77    4269    1809  4375.7  1810.2  4482.4 1812.74
    4589 1811.44  4732.7 1806.79  4881.6 1804.55  4956.4 1803.82  5018.8 1796.34
  5044.5 1804.86  5054.3 1816.01  5066.5 1820.12  5200.1 1821.59  5229.1 1823.02
  5300.6 1836.65  5461.4 1909.76  5512.8 1928.28  5581.7 1943.71  5668.3 1952.31
#Mann= 13 ,-1 , 0
    3580     .12       0  3840.9     .07       0  4102.3     .12       0
    4269     .07       0  4375.7     .12       0  4482.4     .05       0
    4589     .07       0  4732.7     .12       0  4881.6     .07       0
  4956.4     .04       0  5044.5     .07       0  5200.1     .05       0
  5229.1     .12       0
Bank Sta=4956.4,5044.5
XS Rating Curve= 0 ,0
Exp/Cntr=0.3,0.1

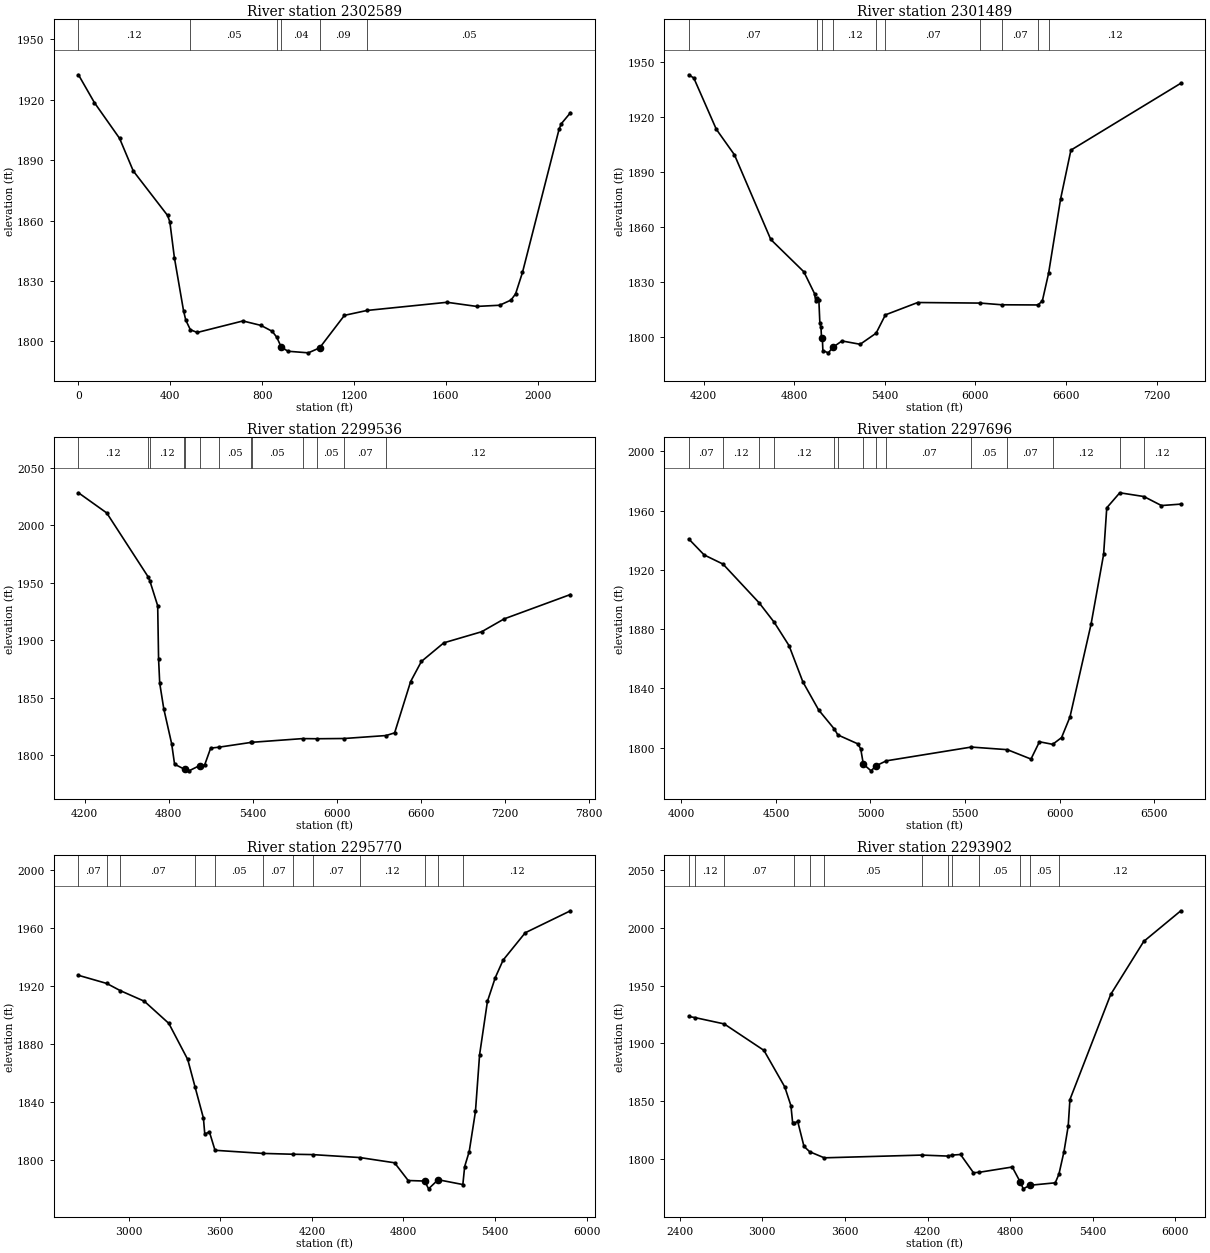
Type RM Length L Ch R = 1 ,2302589 ,1100,1100,1100
XS GIS Cut Line= 4
  1846704.49772113936547.6116542 1846871.016417113935850.9535987
 1847383.169264213935677.3423974 1847417.891307613934791.9258612
#Sta/Elev= 30
       0 1932.39   69.64 1918.53  179.07 1900.82  238.76 1884.63  387.99 1862.56
  397.93 1859.43  417.83 1841.62  457.62 1815.29  467.57 1810.52  487.47 1805.79
  517.32 1804.42  716.28 1810.14  794.94 1807.94   844.1 1804.99  863.77 1802.07
  883.43 1797.14  912.93  1795.1 1001.42 1794.31 1050.58 1796.78 1158.74 1812.93
 1257.06 1815.36 1605.53 1819.41 1734.96 1817.36 1834.52 1817.94  1884.3 1820.52
 1904.21 1823.62 1934.08 1834.21 2093.38 1905.28 2103.34 1908.09 2143.16 1913.55
#Mann= 6 ,-1 , 0
       0     .12       0  487.47     .05       0  863.77      .1       0
  883.43     .04       0 1050.58     .09       0 1257.06     .05       0
Bank Sta=883.43,1050.58
XS Rating Curve= 0 ,0
Exp/Cntr=0.3,0.1

Type RM Length L Ch R = 1 ,2301489 ,1953,1953,1953
BEGIN DESCRIPTION:
Guadalupe River - 201
END DESCRIPTION:
XS GIS Cut Line= 4
      1847302.68     13937039.91      1847935.26     13936428.41
      1847766.57     13934783.62      1847049.82     13934678.22
#Sta/Elev= 30
  4102.7 1943.21    4136 1941.41  4284.7 1913.49  4404.8 1899.55  4645.4 1853.34
  4864.5  1835.7  4935.3 1823.77  4942.2 1820.02  4951.3 1821.62  4963.6 1820.57
  4970.5 1807.58  4977.7 1805.52  4981.4 1799.71  4986.8 1799.71  4990.4 1792.68
  5026.5 1791.48  5056.3 1794.47  5116.6 1797.97  5237.3 1796.15  5342.8  1802.2
  5404.3  1812.2  5618.2 1818.94  6033.5 1818.63  6175.8  1817.7  6414.8 1817.61
  6443.6 1819.83  6484.7 1834.82  6564.2 1875.37  6632.7 1902.09  7360.4 1938.58
#Mann= 10 ,-1 , 0
  4102.7     .07       0  4951.3     .12       0  4986.8     .04       0
  5056.3     .12       0  5342.8     .12       0  5404.3     .07       0
  6033.5     .05       0  6175.8     .07       0  6414.8     .05       0
  6484.7     .12       0
Bank Sta=4986.8,5056.3
XS Rating Curve= 0 ,0
Exp/Cntr=0.3,0.1

Type RM Length L Ch R = 1 ,2299536 ,1840,1840,1840
BEGIN DESCRIPTION:
Guadalupe River - 200
END DESCRIPTION:
XS GIS Cut Line= 3
      1850128.31     13936154.28      1848230.48     13934699.27
      1847112.87     13934636.01
#Sta/Elev= 30
  4156.3 2028.31  4358.2 2010.76  4654.4 1955.04  4665.4 1951.82  4721.7 1930.06
    4728 1883.82  4736.2 1862.68  4765.2 1840.39  4821.4 1810.05  4842.2 1792.25
  4907.8 1788.19  4914.8 1788.22  4945.1 1786.49  5020.8 1791.05  5056.1 1791.34
  5099.7 1806.24  5160.6 1807.09  5389.2 1811.24  5393.8 1811.31  5756.4 1814.53
  5857.9  1814.4  6051.8 1814.61  6351.5 1817.19  6412.4 1819.53  6526.6 1864.13
  6603.3  1881.6  6763.5 1897.82    7034 1907.48  7194.2 1918.65  7667.1 1939.84
#Mann= 13 ,-1 , 0
  4156.3     .12       0  4654.4     .07       0  4665.4     .12       0
  4907.8    .035       0  4914.8     .04       0  5020.8     .12       0
  5160.6     .05       0  5389.2     .12       0  5393.8     .05       0
  5756.4     .07       0  5857.9     .05       0  6051.8     .07       0
  6351.5     .12       0
Bank Sta=4914.8,5020.8
XS Rating Curve= 0 ,0
Exp/Cntr=0.3,0.1

Type RM Length L Ch R = 1 ,2297696 ,1926,1926,1926
BEGIN DESCRIPTION:
Guadalupe River - 199
END DESCRIPTION:
XS GIS Cut Line= 2
      1851203.76     13935437.34      1850023.46     13933118.89
#Sta/Elev= 30
  4039.6 1940.78  4120.8 1930.03  4220.4 1923.86    4412 1897.64  4491.5 1884.52
  4569.6 1868.82  4642.8 1844.35  4726.2 1825.41  4808.8 1812.58  4827.8 1808.56
  4931.9 1802.62  4948.6 1799.24  4962.4 1788.87  5003.3 1784.33  5029.7 1787.74
  5084.2 1791.09    5533 1800.37  5723.9 1798.62  5848.9 1792.28  5893.7 1803.94
  5963.6 1802.22  6010.6 1806.77  6055.1  1820.7  6166.3 1883.11    6233 1930.43
  6249.6 1961.83  6318.5 1971.98  6445.9 1969.45  6538.8 1963.36  6641.2 1964.33
#Mann= 14 ,-1 , 0
  4039.6     .07       0  4220.4     .12       0    4412     .07       0
  4491.5     .12       0  4808.8     .07       0  4827.8     .12       0
  4962.4     .04       0  5029.7     .12       0  5084.2     .07       0
    5533     .05       0  5723.9     .07       0  5963.6     .12       0
  6318.5     .07       0  6445.9     .12       0
Bank Sta=4962.4,5029.7
XS Rating Curve= 0 ,0
Exp/Cntr=0.3,0.1

Type RM Length L Ch R = 1 ,2295770 ,1868,1868,1868
BEGIN DESCRIPTION:
Guadalupe River - 198
END DESCRIPTION:
XS GIS Cut Line= 3
      1851752.03     13935352.94      1852110.49     13934741.45
      1851625.49     13932274.28
#Sta/Elev= 30
    2671 1927.36  2856.6 1921.73  2945.5 1916.75  3102.7 1909.44  3262.9 1894.16
  3386.9 1869.21  3435.2 1850.11  3489.7 1828.72  3498.5 1817.75  3529.1 1819.14
  3565.6 1806.49  3877.9 1804.34  4079.6 1803.75  4204.6 1803.51  4514.7 1801.47
  4741.8 1797.86  4831.2 1785.61  4939.1 1785.24  4964.6 1779.86  5027.2 1786.16
  5189.2 1782.83  5201.2 1795.27    5231 1805.65  5271.8 1833.29  5298.9  1872.5
  5350.3 1909.36  5401.7 1925.78  5453.1 1937.89  5597.9 1956.75  5894.2 1971.94
#Mann= 12 ,-1 , 0
    2671     .07       0  2856.6     .12       0  2945.5     .07       0
  3435.2     .12       0  3565.6     .05       0  3877.9     .07       0
  4079.6     .05       0  4204.6     .07       0  4514.7     .12       0
  4939.1     .04       0  5027.2     .12       0  5189.2     .12       0
Bank Sta=4939.1,5027.2
XS Rating Curve= 0 ,0
Exp/Cntr=0.3,0.1

Type RM Length L Ch R = 1 ,2293902 ,1470,1470,1470
BEGIN DESCRIPTION:
Guadalupe River - 197
END DESCRIPTION:
XS GIS Cut Line= 2
      1851857.43     13935310.83      1853776.38     13932295.33
#Sta/Elev= 30
  2465.9 1923.29    2509 1922.39  2722.8 1916.87  3011.5    1894    3163 1862.36
  3207.7 1846.16  3220.6 1830.94  3232.6 1831.03    3257 1832.52  3302.5 1810.98
  3344.1 1806.29    3450 1801.04  4157.7 1803.41  4345.7 1802.56  4378.2 1803.38
  4439.8 1803.92  4533.8 1788.17  4574.7  1788.5  4815.7 1793.09  4873.3 1780.24
  4895.8 1774.21  4943.3 1777.29  5127.9 1779.42  5154.5 1786.81  5191.6  1806.5
  5222.1 1828.51  5234.6 1851.42  5531.1 1942.43  5770.7 1988.21  6040.2 2014.74
#Mann= 13 ,-1 , 0
  2465.9     .07       0    2509     .12       0  2722.8     .07       0
  3232.6     .12       0  3344.1     .07       0    3450     .05       0
  4157.7     .07       0  4345.7     .05       0  4378.2     .07       0
  4574.7     .05       0  4873.3     .04       0  4943.3     .05       0
  5154.5     .12       0
Bank Sta=4873.3,4943.3
XS Rating Curve= 0 ,0
Exp/Cntr=0.3,0.1

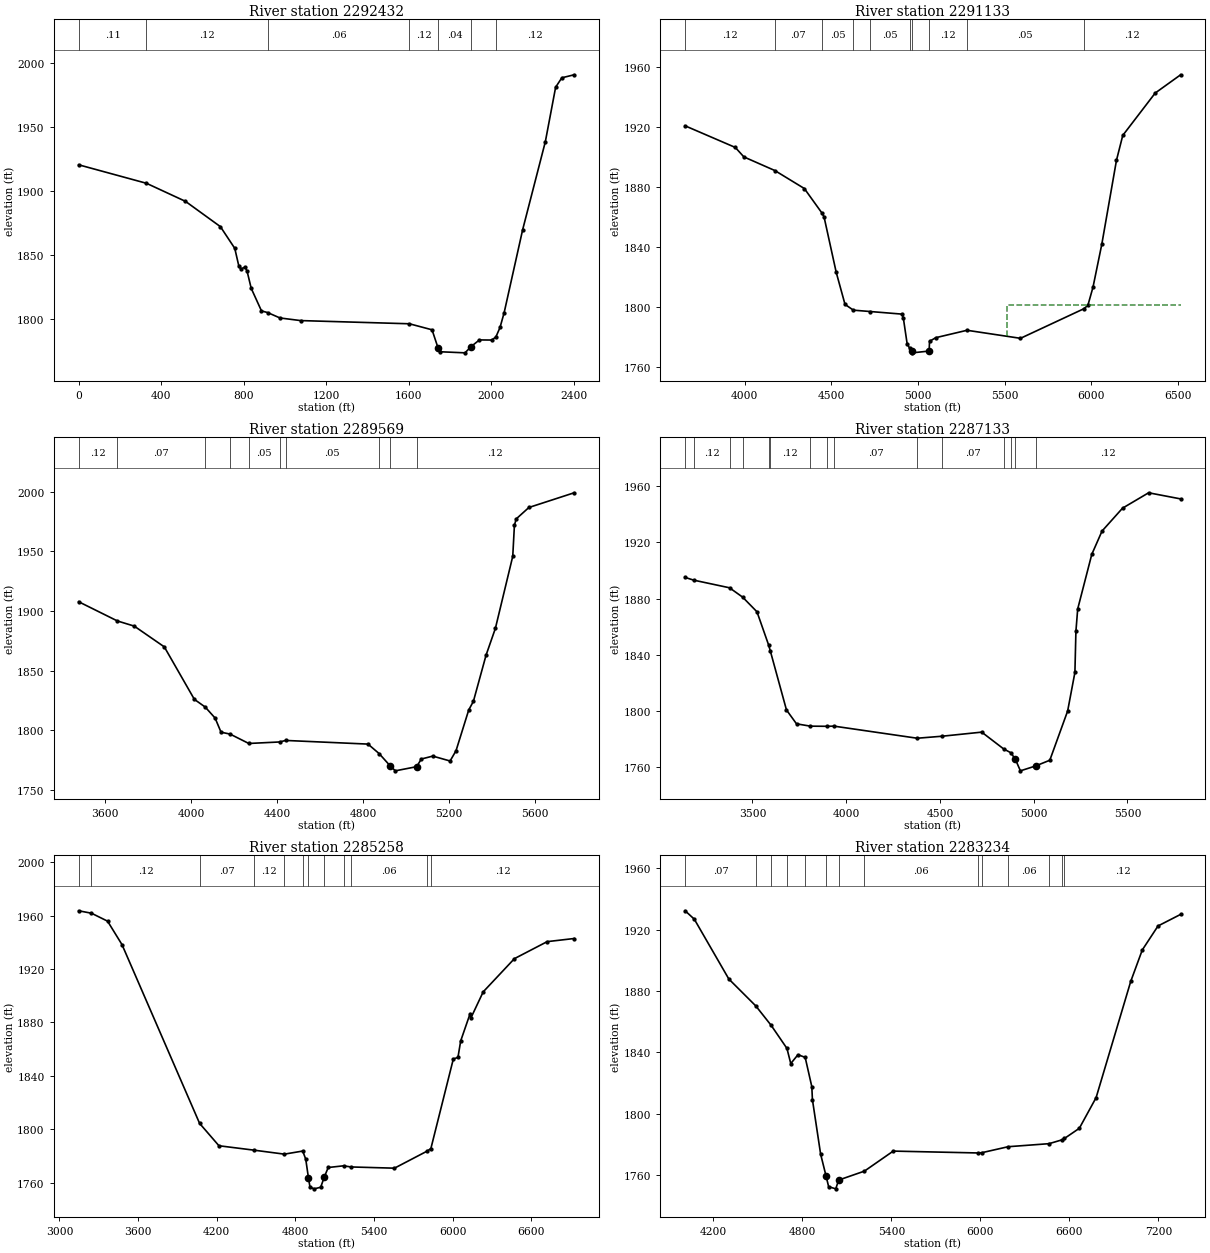
Type RM Length L Ch R = 1 ,2292432 ,1299,1299,1299
XS GIS Cut Line= 3
   1851957.8218613935243.3147222  1853398.79404413934453.3842154
 1854015.113677513934010.6757832
#Sta/Elev= 30
       0 1920.75  328.66 1906.31  517.88  1892.2  687.19 1872.44  756.91 1855.48
  776.83 1841.48  786.79 1839.31   806.7  1840.9  816.66 1837.59  836.58 1824.26
  886.38 1806.62  916.26 1805.32  976.01 1801.11 1075.61 1799.07 1603.45 1796.57
 1713.18 1791.86 1743.13 1777.29 1753.12 1774.71 1872.94 1773.87 1902.89 1778.82
 1942.83 1783.96 2002.74 1783.86 2022.71 1786.31 2042.68 1793.68 2062.65 1805.22
 2152.51 1870.12 2262.34 1938.77 2312.27 1981.33 2342.22  1988.7 2402.13 1991.06
#Mann= 7 ,-1 , 0
       0     .11       0  328.66     .12       0  916.26     .06       0
 1603.45     .12       0 1743.13     .04       0 1902.89     .07       0
 2022.71     .12       0
Bank Sta=1743.13,1902.89
XS Rating Curve= 0 ,0
Exp/Cntr=0.3,0.1

Type RM Length L Ch R = 1 ,2291133 ,1564,1564,1564
BEGIN DESCRIPTION:
Guadalupe River - 196
END DESCRIPTION:
XS GIS Cut Line= 4
      1852644.42     13936281.78      1853516.83     13935582.98
      1854007.28     13935257.46      1854961.06     13934607.15
#Sta/Elev= 30
  3655.2 1921.03  3945.1 1906.59  3994.7 1900.26    4173 1891.19  4343.6 1879.16
  4444.5 1862.92  4457.3 1860.27  4527.7 1823.17  4578.4  1801.8  4626.7 1797.94
  4723.5 1797.04  4906.9 1795.31  4914.8 1792.94    4937 1775.58  4951.5 1772.49
  4966.1 1770.65  4967.6 1769.45  5064.1 1770.65  5066.3 1777.14  5102.3 1779.57
  5282.7 1784.51  5591.4 1779.14  5955.6  1798.8  5980.3 1801.06  6010.1 1813.31
  6060.8 1841.92  6145.6 1898.03  6181.9 1914.63  6369.2 1942.92    6516 1955.11
#Mann= 10 ,-1 , 0
  3655.2     .12       0    4173     .07       0  4444.5     .05       0
  4626.7     .07       0  4723.5     .05       0  4951.5     .07       0
  4966.1     .05       0  5064.1     .12       0  5282.7     .05       0
  5955.6     .12       0
#XS Ineff= 2 , 0
       0                 5515.39       0 1801.35
Permanent Ineff=
       F       F
Bank Sta=4966.1,5064.1
XS Rating Curve= 0 ,0
Exp/Cntr=0.3,0.1

Type RM Length L Ch R = 1 ,2289569 ,2436,2436,2436
BEGIN DESCRIPTION:
Guadalupe River - 195
END DESCRIPTION:
XS GIS Cut Line= 2
      1853523.34     13936976.66      1855526.63     13935837.95
#Sta/Elev= 30
    3478 1907.68  3658.4 1891.55  3736.5 1887.25  3876.4 1869.84  4016.2 1825.84
  4066.6  1819.4  4112.6 1810.17  4140.2 1798.31  4182.1 1796.75  4269.3 1788.87
  4413.2 1790.14  4440.4 1791.41  4823.5 1788.35  4875.3  1780.4  4925.9 1770.26
  4950.7 1765.93  5049.8 1769.42  5071.5 1775.84  5124.8 1778.28  5205.3 1774.18
  5232.9 1782.79    5292 1816.97  5313.7 1824.18  5372.8 1863.02    5416 1885.39
  5496.7 1945.77  5504.4 1971.67  5512.6 1977.07  5571.7 1986.67  5782.3    1999
#Mann= 10 ,-1 , 0
    3478     .12       0  3658.4     .07       0  4066.6     .05       0
  4182.1     .07       0  4269.3     .05       0  4413.2     .07       0
  4440.4     .05       0  4875.3     .07       0  4925.9     .04       0
  5049.8     .12       0
Bank Sta=4925.9,5049.8
XS Rating Curve= 0 ,0
Exp/Cntr=0.3,0.1

Type RM Length L Ch R = 1 ,2287133 ,1875,1875,1875
BEGIN DESCRIPTION:
Guadalupe River - 194
END DESCRIPTION:
XS GIS Cut Line= 2
      1854240.28      13938726.9      1856707.48     13937777.97
#Sta/Elev= 30
  3140.7 1895.01  3186.7 1893.06  3377.7 1887.63  3447.6 1880.97  3524.1 1870.55
  3586.2 1846.93  3595.1 1842.78  3681.5 1800.68    3735 1790.83    3809 1789.17
  3898.3 1789.07  3935.3 1789.18  4378.9 1780.58  4512.3 1782.02    4723 1784.92
  4839.9 1772.98  4878.6 1770.24  4902.9 1765.46  4929.3 1757.38    5010 1760.83
  5086.2 1764.92  5181.4 1799.98  5220.1 1827.41  5225.5 1856.74    5235 1872.59
  5310.1 1911.41  5364.8 1927.99  5474.1 1944.27  5613.3 1955.23  5784.1 1950.87
#Mann= 15 ,-1 , 0
  3140.7     .07       0  3186.7     .12       0  3377.7     .07       0
  3447.6     .12       0  3586.2     .07       0  3595.1     .12       0
    3809     .07       0  3898.3     .12       0  3935.3     .07       0
  4378.9     .05       0  4512.3     .07       0  4839.9     .05       0
  4878.6     .12       0  4902.9     .04       0    5010     .12       0
Bank Sta=4902.9,5010
XS Rating Curve= 0 ,0
Exp/Cntr=0.3,0.1

Type RM Length L Ch R = 1 ,2285258 ,2024,2024,2024
BEGIN DESCRIPTION:
Guadalupe River - 193
END DESCRIPTION:
XS GIS Cut Line= 4
      1854514.44      13940181.9      1855568.76     13940139.72
      1857065.94     13938958.85      1856897.51     13938158.79
#Sta/Elev= 30
  3146.5 1963.56  3244.2 1961.74  3367.2 1955.79  3477.3 1938.23  4069.1 1804.47
  4216.7 1787.72  4485.3 1784.41  4715.6 1781.44  4855.8 1783.76  4878.8 1777.63
  4899.7 1763.46  4911.3 1756.68  4943.7 1755.48  4992.7 1756.68  5021.6 1764.65
  5050.2 1771.45  5167.1 1772.71  5222.9 1771.86  5555.4 1770.94  5805.8 1783.77
  5833.2 1785.65  6004.4 1852.66  6039.7 1853.85  6060.5 1866.16  6132.5 1886.62
  6137.7 1883.21  6232.2 1902.88  6470.1 1927.72  6720.2 1940.47  6926.1 1942.81
#Mann= 12 ,-1 , 0
  3146.5     .07       0  3244.2     .12       0  4069.1     .07       0
  4485.3     .12       0  4715.6     .07       0  4855.8     .12       0
  4899.7     .04       0  5021.6     .12       0  5167.1     .05       0
  5222.9     .06       0  5805.8     .07       0  5833.2     .12       0
Bank Sta=4899.7,5021.6
XS Rating Curve= 0 ,0
Exp/Cntr=0.3,0.1

Type RM Length L Ch R = 1 ,2283234 ,2054,2054,2054
BEGIN DESCRIPTION:
Guadalupe River - 192
END DESCRIPTION:
XS GIS Cut Line= 4
      1857593.13     13941953.24       1857297.9      13941151.9
      1857909.42     13939507.11      1858415.47     13938979.98
#Sta/Elev= 30
    4010 1932.34  4071.8 1926.89  4304.8 1887.82  4486.7 1870.25  4590.2 1857.58
  4696.3 1842.58  4722.1 1832.69  4770.6 1838.45  4819.2 1836.74    4864  1817.6
    4868  1809.2  4923.4 1773.56  4959.1 1759.66  4977.3 1752.37  5025.3 1750.97
  5044.8 1756.69  5218.4 1762.52  5412.7 1775.59  5984.9 1774.37    6009 1774.53
  6187.3 1778.45  6462.7 1780.43  6549.5 1782.92  6566.4 1783.83  6666.6 1790.44
  6779.8 1810.46  7013.1 1886.25  7091.1  1906.8  7197.1 1922.44  7349.5 1929.99
#Mann= 14 ,-1 , 0
    4010     .07       0  4486.7     .05       0  4590.2     .12       0
  4696.3     .05       0  4819.2     .07       0  4959.1     .04       0
  5044.8     .07       0  5218.4     .06       0  5984.9     .07       0
    6009     .06       0  6187.3     .06       0  6462.7     .12       0
  6549.5     .07       0  6566.4     .12       0
Bank Sta=4959.1,5044.8
XS Rating Curve= 0 ,0
Exp/Cntr=0.3,0.1