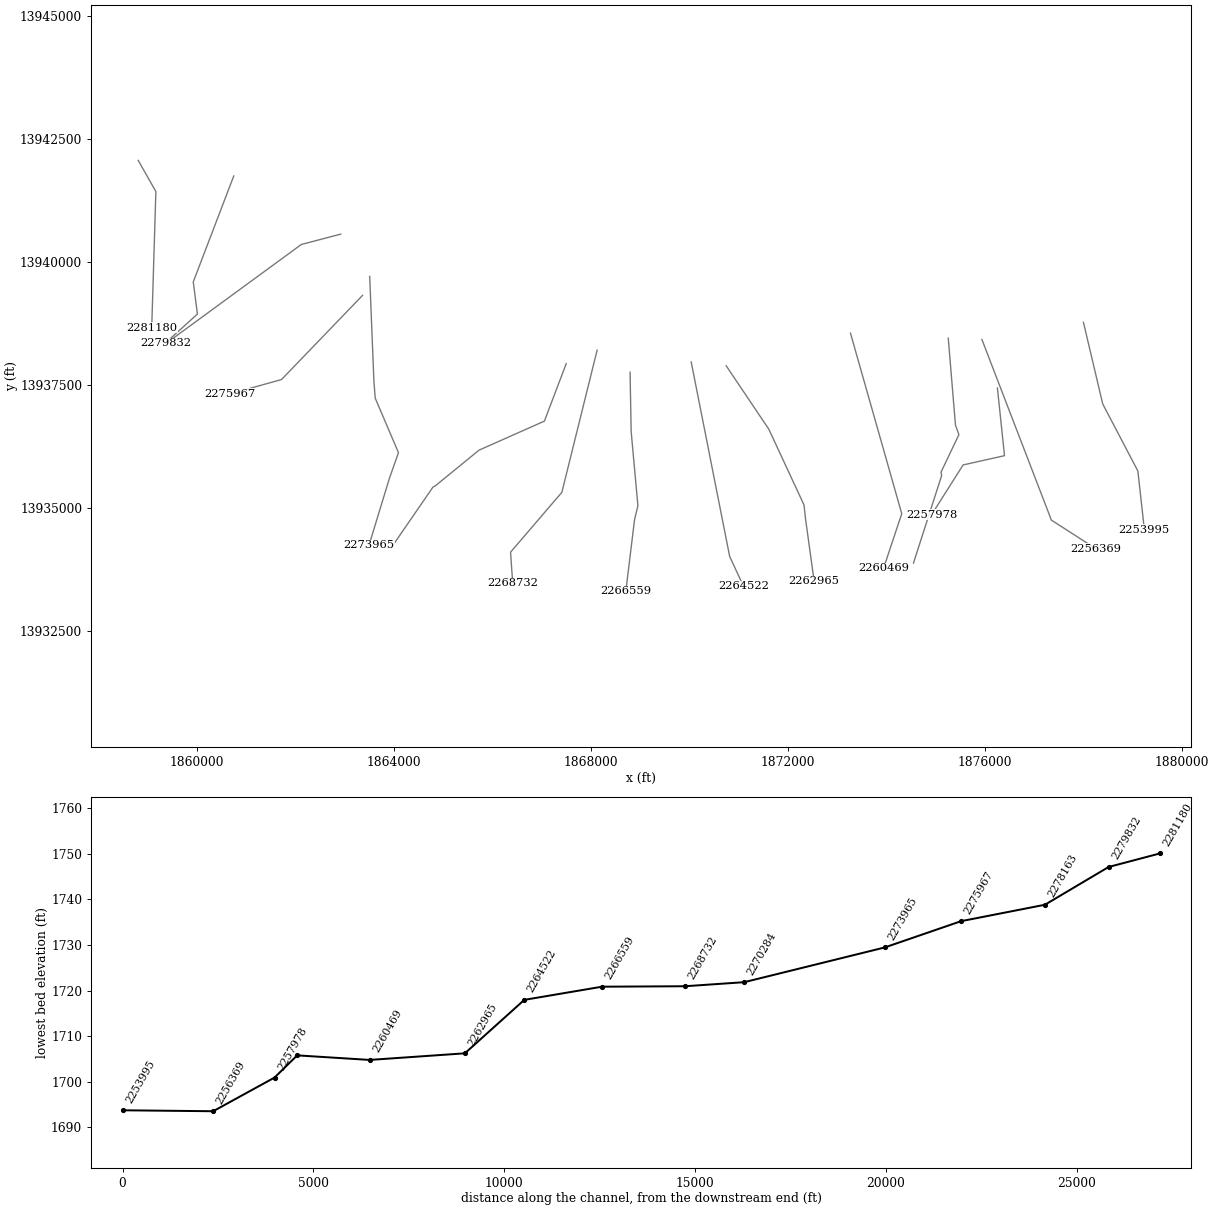
HEC-RAS study Guadalupe River.prj: Guadalupe River Base Level Engineering

--- Guadalupe River.g01 (geometry) --- (continued)

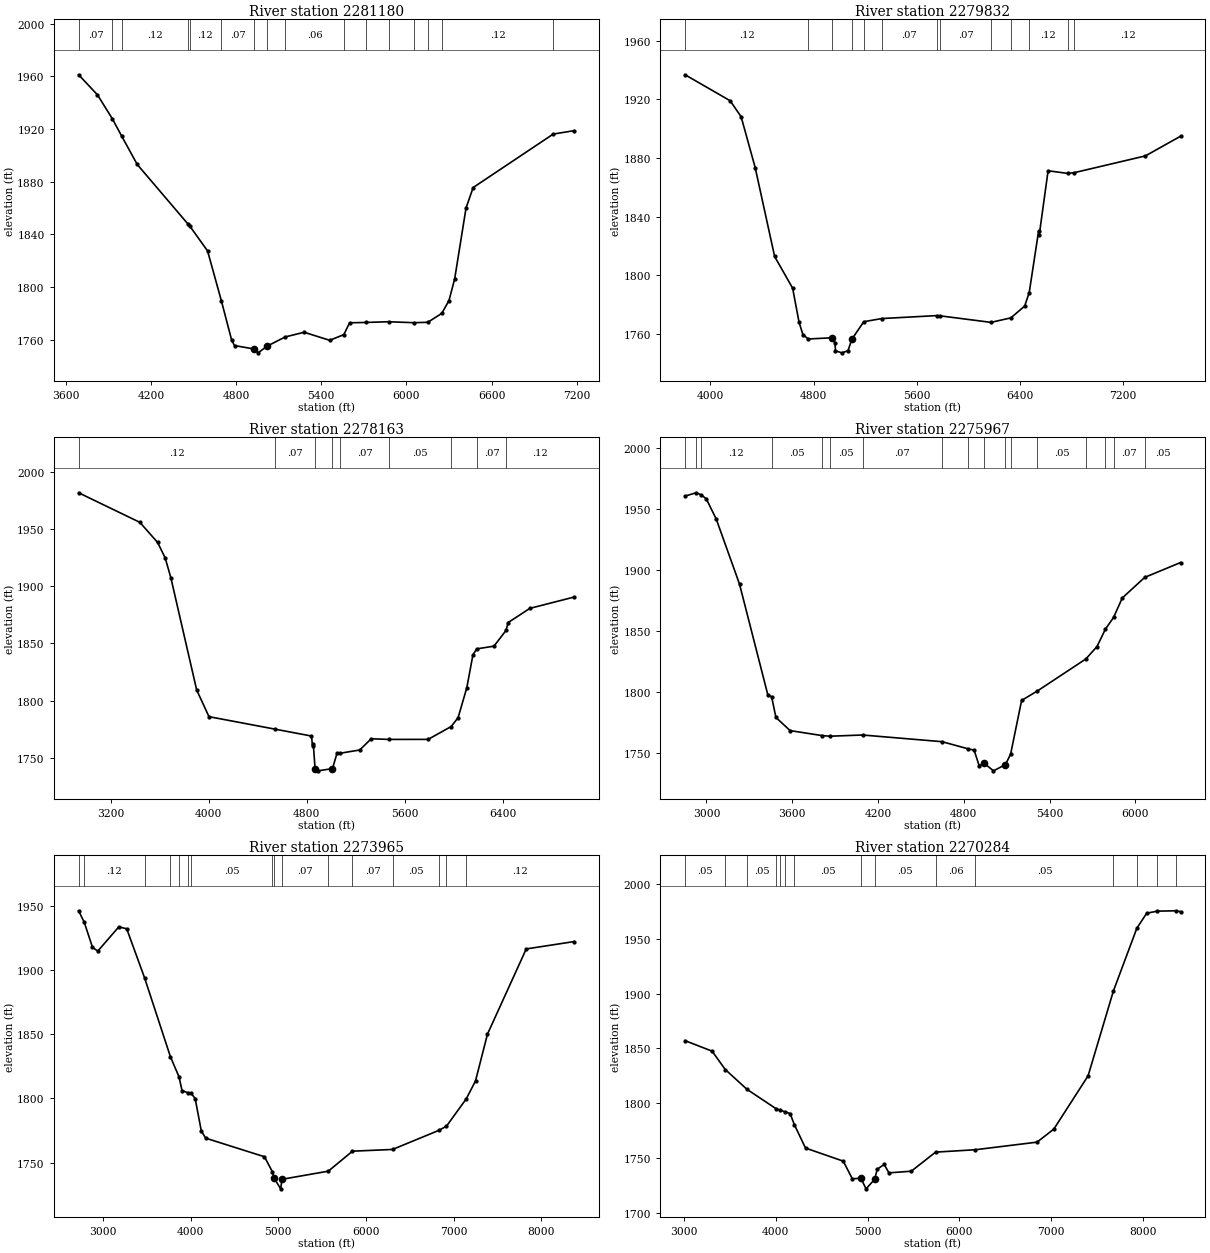
Type RM Length L Ch R = 1 ,2281180 ,1348,1348,1348
BEGIN DESCRIPTION:
Guadalupe River - 191
END DESCRIPTION:
XS GIS Cut Line= 3
      1858816.16     13942058.65      1859174.64     13941426.03
      1859090.29     13938663.64
#Sta/Elev= 30
  3691.3  1961.1  3824.2 1945.85    3929 1927.68  3995.1 1914.46  4104.1 1893.05
  4463.8 1847.56  4472.7 1846.53  4599.5 1827.46  4696.4 1789.76  4769.6 1759.61
  4789.6 1755.64  4929.7 1752.98  4955.5 1750.11  5019.7 1755.22  5146.8 1762.19
  5279.9 1765.72  5459.9 1759.62  5559.5 1763.93    5600  1772.9  5714.6 1773.17
  5874.7 1773.71  6052.6 1772.98  6151.1 1773.29  6249.6 1780.07  6300.3 1789.82
  6340.4 1806.29  6420.4 1860.02  6470.4 1875.52  7034.3  1916.1  7182.1  1918.7
#Mann= 16 ,-1 , 0
  3691.3     .07       0    3929     .12       0  3995.1     .12       0
  4463.8     .05       0  4472.7     .12       0  4696.4     .07       0
  4929.7     .04       0  5019.7     .07       0  5146.8     .06       0
  5559.5     .07       0  5714.6     .12       0  5874.7     .05       0
  6052.6     .12       0  6151.1     .05       0  6249.6     .12       0
  7034.3     .07       0
Bank Sta=4929.7,5019.7
XS Rating Curve= 0 ,0
Exp/Cntr=0.3,0.1

Type RM Length L Ch R = 1 ,2279832 ,1669,1669,1669
BEGIN DESCRIPTION:
Guadalupe River - 190
END DESCRIPTION:
XS GIS Cut Line= 4
      1860756.18     13941742.38      1859933.77     13939591.46
      1860018.12     13938937.76      1859365.89     13938348.65
#Sta/Elev= 30
  3804.6 1936.71  4153.8 1919.01  4238.7 1908.13  4347.8 1873.44  4498.5 1812.83
  4638.1 1791.21  4687.5 1768.12  4717.5 1759.58  4759.4 1756.58    4942 1757.39
  4966.7  1753.9  4970.1 1748.53    5020 1747.13  5066.8 1748.53  5097.2 1756.41
  5189.2 1768.34  5328.1  1770.5  5756.7 1772.53  5783.7 1772.33  6175.5  1767.9
  6329.8 1770.98  6436.6 1779.02  6471.8 1788.24  6544.6 1830.18  6549.6 1827.56
    6618 1871.28  6768.9 1869.47  6821.3 1869.98  7372.6 1881.41  7645.4 1894.85
#Mann= 13 ,-1 , 0
  3804.6     .12       0  4759.4     .05       0    4942     .04       0
  5097.2     .05       0  5189.2     .05       0  5328.1     .07       0
  5756.7     .05       0  5783.7     .07       0  6175.5     .05       0
  6329.8     .07       0  6471.8     .12       0  6768.9     .07       0
  6821.3     .12       0
Bank Sta=4942,5097.2
XS Rating Curve= 0 ,0
Exp/Cntr=0.3,0.1

Type RM Length L Ch R = 1 ,2278163 ,2196,2196,2196
BEGIN DESCRIPTION:
Guadalupe River - 189
END DESCRIPTION:
XS GIS Cut Line= 3
      1862928.09     13940561.45      1862126.82     13940350.59
      1859533.14     13938452.78
#Sta/Elev= 30
  2939.8 1981.48  3439.3 1955.68  3584.1 1938.14  3646.1 1924.58  3692.4 1907.19
  3902.8 1809.37  4003.1 1786.11  4541.3 1775.23  4839.3  1769.2  4847.8 1760.64
    4854 1762.28  4868.7 1740.68  4892.2 1738.84  5010.7  1740.8  5046.9 1754.02
    5076 1754.26  5232.8 1757.03  5326.5 1766.83  5472.1 1766.26  5790.6  1766.3
  5979.3 1777.52  6035.3 1785.25  6106.3 1811.34  6156.5 1840.14  6188.2 1845.29
  6327.9 1847.63  6426.9 1861.45  6442.9 1868.18  6620.6 1880.61  6982.2  1890.5
#Mann= 9 ,-1 , 0
  2939.8     .12       0  4541.3     .07       0  4868.7     .04       0
  5010.7     .07       0    5076     .07       0  5472.1     .05       0
  5979.3     .12       0  6188.2     .07       0  6426.9     .12       0
Bank Sta=4868.7,5010.7
XS Rating Curve= 0 ,0
Exp/Cntr=0.3,0.1

Type RM Length L Ch R = 1 ,2275967 ,2002,2002,2002
BEGIN DESCRIPTION:
Guadalupe River - 188
END DESCRIPTION:
XS GIS Cut Line= 3
      1863370.98     13939317.36      1861726.17     13937609.28
      1860671.79     13937314.06
#Sta/Elev= 30
  2850.8 1960.59  2927.3 1963.32  2960.5 1961.76  2998.1 1958.54  3068.9 1941.67
  3231.4 1888.41  3429.5 1797.58    3456    1796  3486.1 1779.02  3585.2 1768.25
  3805.9 1764.21  3862.4 1763.64  4092.9 1764.63    4648 1759.16  4832.7 1753.22
  4872.3 1752.24  4907.8 1739.41    4943  1741.4  5007.9 1735.24  5091.5 1740.37
  5127.7 1748.94  5204.7 1793.01  5314.1 1800.68  5653.7 1826.98  5732.1  1837.2
  5790.5 1851.42  5847.9 1861.08  5908.7 1877.02  6065.6 1893.91    6317 1906.13
#Mann= 17 ,-1 , 0
  2850.8     .08       0  2927.3     .05       0  2960.5     .12       0
    3456     .05       0  3805.9     .07       0  3862.4     .05       0
  4092.9     .07       0    4648     .12       0  4832.7     .07       0
    4943     .04       0  5091.5     .07       0  5127.7     .12       0
  5314.1     .05       0  5653.7     .07       0  5790.5     .12       0
  5847.9     .07       0  6065.6     .05       0
Bank Sta=4943,5091.5
XS Rating Curve= 0 ,0
Exp/Cntr=0.3,0.1

Type RM Length L Ch R = 1 ,2273965 ,3681,3681,3681
BEGIN DESCRIPTION:
Guadalupe River - 187
END DESCRIPTION:
XS GIS Cut Line= 6
      1863516.03     13939702.96      1863601.48     13937575.01
      1863628.13     13937231.33      1864100.23     13936124.17
      1863916.44     13935603.44      1863501.62      13934243.6
#Sta/Elev= 30
  2722.2 1946.54  2786.3 1937.54  2880.3 1918.03  2940.3 1915.03  3180.5 1933.97
  3270.6 1932.49  3474.4 1894.17  3769.3 1832.54  3867.6 1816.84  3901.1  1806.2
  3965.9 1804.54  4002.4 1804.35  4051.2 1799.99  4121.3 1774.66  4171.3 1769.03
  4841.9 1754.51  4931.2  1742.9  4952.2 1737.78  5026.2 1729.47  5042.4 1736.93
  5569.7 1743.26  5845.7 1758.87  6302.4 1760.22  6829.9 1775.08  6917.6 1778.39
  7143.3 1799.73  7248.7 1813.71  7385.2 1850.23  7827.5 1916.76  8374.1  1922.5
#Mann= 16 ,-1 , 0
  2722.2     .07       0  2786.3     .12       0  3474.4     .05       0
  3769.3     .12       0  3867.6     .05       0  3965.9     .07       0
  4002.4     .05       0  4931.2     .07       0  4952.2     .04       0
  5042.4     .07       0  5569.7     .05       0  5845.7     .07       0
  6302.4     .05       0  6829.9     .12       0  6917.6     .07       0
  7143.3     .12       0
Bank Sta=4952.2,5042.4
XS Rating Curve= 0 ,0
Exp/Cntr=0.3,0.1

Type RM Length L Ch R = 1 ,2270284 ,1552,1552,1552
BEGIN DESCRIPTION:
Guadalupe River - 186
END DESCRIPTION:
XS GIS Cut Line= 6
      1867506.06     13937931.12      1867063.27     13936764.93
      1865735.33     13936174.73      1864847.35     13935449.75
      1864801.32     13935425.92      1863949.06      13934187.3
#Sta/Elev= 30
  3011.2 1856.99  3305.6 1847.41  3449.3 1830.68  3685.6 1812.63  4005.1 1794.81
  4046.3 1793.64  4100.3 1792.11    4156 1790.54    4202 1780.43  4323.9 1759.05
  4735.7 1747.09  4834.2 1731.03  4927.6 1731.48  4983.9 1721.85  5077.5 1730.49
  5106.4 1739.82  5181.6 1744.06  5233.6 1736.43  5477.1 1737.94  5742.1 1755.33
  6176.2 1757.52  6848.3 1764.44  7031.1 1776.35  7404.5 1824.91  7680.3 1902.26
    7936 1959.52  8043.7 1973.27  8159.8 1975.12  8365.4 1975.46  8413.5 1974.66
#Mann= 15 ,-1 , 0
  3011.2     .05       0  3449.3     .08       0  3685.6     .05       0
  4005.1     .07       0  4046.3     .05       0  4100.3     .12       0
    4202     .05       0  4927.6     .04       0  5077.5     .05       0
  5742.1     .06       0  6176.2     .05       0  7680.3     .12       0
    7936     .08       0  8159.8     .12       0  8365.4     .05       0
Bank Sta=4927.6,5077.5
XS Rating Curve= 0 ,0
Exp/Cntr=0.3,0.1

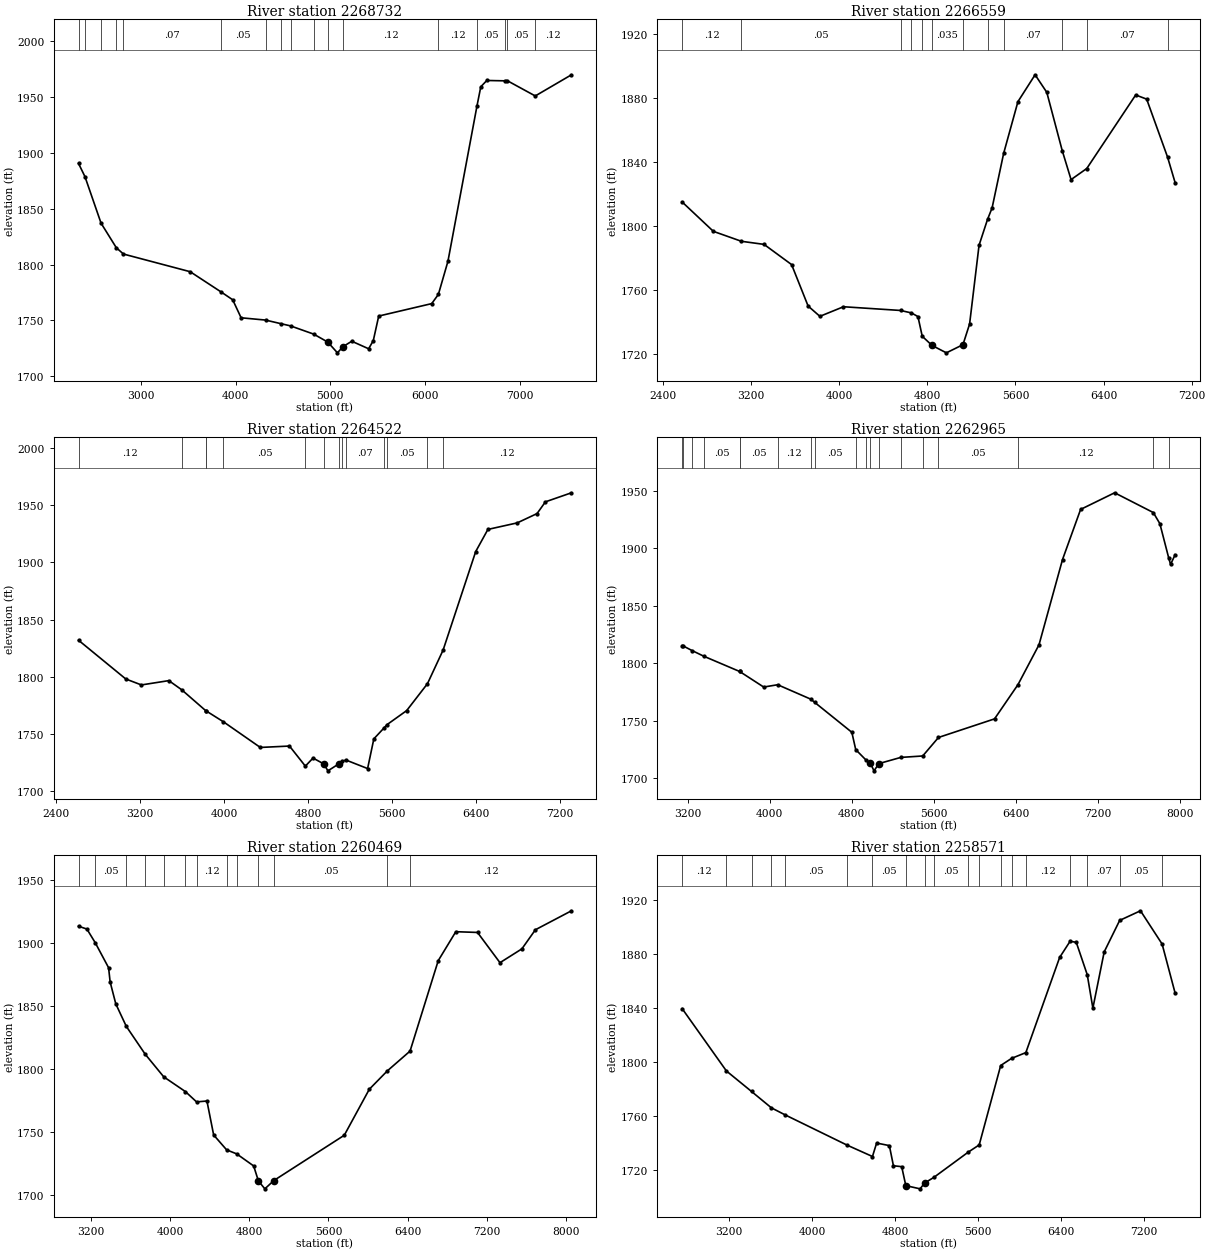
Type RM Length L Ch R = 1 ,2268732 ,2173,2173,2173
BEGIN DESCRIPTION:
Guadalupe River - 185
END DESCRIPTION:
XS GIS Cut Line= 4
      1868133.79     13938205.17      1867417.63     13935318.84
      1866375.97     13934103.57      1866419.37     13933474.22
#Sta/Elev= 30
  2341.4 1890.61  2409.5 1878.78  2579.7 1837.06  2741.2 1815.04  2816.5 1809.43
  3520.6 1793.62  3843.6 1775.69  3969.5  1768.5  4058.4 1752.35  4316.3 1750.31
  4477.7  1747.1  4579.9  1745.1  4824.6 1737.74  4973.2 1730.61  5075.5 1720.96
  5133.7 1726.49    5227 1731.35  5404.9 1724.61  5454.2 1731.96  5511.3  1753.9
  6071.1 1765.06  6141.3 1773.29  6242.3 1802.95  6549.3 1942.25  6589.1 1959.26
  6652.8 1964.91  6840.4 1964.59  6866.9 1964.81  7164.3 1951.04  7546.7 1970.01
#Mann= 17 ,-1 , 0
  2341.4     .07       0  2409.5     .12       0  2579.7     .05       0
  2741.2     .12       0  2816.5     .07       0  3843.6     .05       0
  4316.3     .07       0  4477.7     .12       0  4579.9     .05       0
  4824.6     .12       0  4973.2     .04       0  5133.7     .12       0
  6141.3     .12       0  6549.3     .05       0  6840.4     .12       0
  6866.9     .05       0  7164.3     .12       0
Bank Sta=4973.2,5133.7
XS Rating Curve= 0 ,0
Exp/Cntr=0.3,0.1

Type RM Length L Ch R = 1 ,2266559 ,2037,2037,2037
BEGIN DESCRIPTION:
Guadalupe River - 184
END DESCRIPTION:
XS GIS Cut Line= 6
      1868802.48     13937758.33      1868824.83     13936552.13
      1868909.39     13935621.86      1868961.66     13935047.11
      1868893.94     13934767.24      1868716.22     13933308.71
#Sta/Elev= 30
  2574.4 1815.08  2857.8 1796.74  3112.4 1790.53  3317.9  1788.6  3567.9 1775.98
  3717.9 1750.09  3824.8 1743.66    4039 1749.65  4556.8 1747.33  4655.3  1745.8
  4714.9 1743.51  4753.8 1731.22  4842.3 1725.51    4973 1720.86  5123.5 1725.96
  5183.7 1738.87  5269.6 1788.06  5346.5  1804.2    5388 1811.39    5493 1845.49
  5622.5 1877.74  5778.3 1894.53  5884.5 1883.56  6024.3 1847.23  6104.8 1829.06
  6247.4 1835.99  6691.4 1881.92  6791.1 1879.32  6980.6 1843.15  7049.3 1827.16
#Mann= 12 ,-1 , 0
  2574.4     .12       0  3112.4     .05       0  4556.8     .07       0
  4655.3     .05       0  4753.8     .12       0  4842.3    .035       0
  5123.5     .05       0  5346.5     .12       0    5493     .07       0
  6024.3     .12       0  6247.4     .07       0  6980.6     .05       0
Bank Sta=4842.3,5123.5
XS Rating Curve= 0 ,0
Exp/Cntr=0.3,0.1

Type RM Length L Ch R = 1 ,2264522 ,1557,1557,1557
BEGIN DESCRIPTION:
Guadalupe River - 183
END DESCRIPTION:
XS GIS Cut Line= 3
      1870043.51     13937966.39      1870824.75     13934016.76
      1871106.66     13933409.57
#Sta/Elev= 30
  2612.4 1832.09  3062.8 1798.22  3211.5 1793.02  3472.8 1796.79    3595 1788.83
  3827.9 1770.24    3830 1770.22  3993.5 1760.78  4344.1 1738.41    4622 1739.63
  4773.1 1722.09  4846.3 1729.13  4948.2 1724.04  4988.2 1717.97  5090.9 1724.01
  5126.3 1726.44  5161.3 1727.35  5366.1 1719.97  5425.5 1745.91  5525.4 1755.73
  5551.7 1758.37  5738.1 1770.59  5936.3 1794.11  6085.6 1823.56  6395.7 1909.54
    6512  1928.9  6791.4 1934.61  6980.1 1942.74  7059.8    1953    7308 1960.91
#Mann= 14 ,-1 , 0
  2612.4     .12       0    3595     .07       0  3827.9     .05       0
    3830     .07       0  3993.5     .05       0  4773.1     .07       0
  4948.2     .04       0  5090.9     .12       0  5126.3     .05       0
  5161.3     .07       0  5525.4     .12       0  5551.7     .05       0
  5936.3     .07       0  6085.6     .12       0
Bank Sta=4948.2,5090.9
XS Rating Curve= 0 ,0
Exp/Cntr=0.3,0.1

Type RM Length L Ch R = 1 ,2262965 ,2496,2496,2496
BEGIN DESCRIPTION:
Guadalupe River - 182
END DESCRIPTION:
XS GIS Cut Line= 6
      1870754.27     13937887.99       1871619.2     13936601.28
      1872334.47     13935061.68      1872340.36     13935007.28
      1872363.93     13934788.52      1872540.15      13933511.1
#Sta/Elev= 30
  3144.7 1815.11  3149.2 1815.11  3241.4 1810.86  3357.4 1805.87  3705.3 1792.68
  3706.1 1792.65  3940.6 1779.12  4077.4 1781.12  4401.4 1768.54  4436.9 1765.91
  4801.3 1739.76  4839.3 1724.68  4934.7 1716.07  4982.5 1712.71  5017.7 1706.24
  5065.9 1712.56  5279.4 1717.92  5493.1 1719.17  5647.2 1735.28  6194.2 1751.43
  6423.1 1781.22  6628.3 1815.86    6858 1890.05  7034.4 1933.61  7366.5 1948.08
    7744 1930.89  7808.1 1921.23  7893.9 1891.61  7912.7 1885.76    7957 1894.21
#Mann= 19 ,-1 , 0
  3144.7     .07       0  3149.2     .05       0  3241.4     .12       0
  3357.4     .05       0  3705.3     .07       0  3706.1     .05       0
  4077.4     .12       0  4401.4     .08       0  4436.9     .05       0
  4839.3     .12       0  4934.7     .05       0  4982.5     .04       0
  5065.9     .05       0  5279.4     .07       0  5493.1     .12       0
  5647.2     .05       0  6423.1     .12       0    7744     .07       0
  7893.9     .12       0
Bank Sta=4982.5,5065.9
XS Rating Curve= 0 ,0
Exp/Cntr=0.3,0.1

Type RM Length L Ch R = 1 ,2260469 ,1898,1898,1898
BEGIN DESCRIPTION:
Guadalupe River - 181
END DESCRIPTION:
XS GIS Cut Line= 3
      1873277.01     13938552.35      1874318.68     13934884.82
      1873950.21     13933779.41
#Sta/Elev= 30
  3076.4 1913.59  3161.3 1911.33  3245.1 1900.51  3380.2  1880.6  3395.9 1869.25
  3453.2 1851.79  3559.2 1833.95  3750.3 1811.78    3937 1793.84  4156.3 1782.09
  4268.4 1773.92  4373.3 1774.62  4441.1 1747.62  4572.4 1735.76  4673.7 1732.59
  4845.1 1722.99  4892.9 1711.09  4958.1 1704.79  5048.8 1711.39  5760.1 1747.39
  6012.9 1783.98  6194.9 1798.58  6424.3 1814.31  6708.9 1886.23  6886.3 1909.24
  7105.5 1908.64  7332.2  1884.6  7553.5 1895.59  7689.9 1910.78  8054.2 1925.87
#Mann= 13 ,-1 , 0
  3076.4     .07       0  3245.1     .05       0  3559.2     .07       0
  3750.3     .05       0    3937     .12       0  4156.3     .05       0
  4268.4     .12       0  4572.4     .07       0  4673.7     .05       0
  4892.9     .04       0  5048.8     .05       0  6194.9     .05       0
  6424.3     .12       0
Bank Sta=4892.9,5048.8
XS Rating Curve= 0 ,0
Exp/Cntr=0.3,0.1

Type RM Length L Ch R = 1 ,2258571 ,593,593,593
BEGIN DESCRIPTION:
Guadalupe River - 180
END DESCRIPTION:
XS GIS Cut Line= 6
       1875262.9     13938449.71      1875409.41     13936682.88
       1875479.4     13936490.46      1875116.14     13935729.32
      1875128.69     13935659.05      1874557.07      13933883.5
#Sta/Elev= 30
  2746.3 1839.23  3173.5 1793.06  3416.1 1777.87  3607.7 1765.76  3737.8 1760.64
  4337.7 1738.17  4583.1 1729.73  4623.3 1739.69  4746.2  1737.8  4785.4 1722.88
  4865.2 1722.21    4905 1708.17  5042.7 1705.79  5086.4 1710.09  5175.7 1714.27
  5507.7 1732.98  5613.2 1738.31  5820.7  1797.1  5925.1 1802.36  6063.3 1806.65
  6389.5  1877.1  6490.3 1889.07  6549.9 1888.33  6655.9 1864.35  6710.3 1839.59
  6819.6 1881.24  6969.1 1904.54  7169.8 1911.66  7378.5 1887.04    7504 1850.72
#Mann= 19 ,-1 , 0
  2746.3     .12       0  3173.5     .07       0  3416.1     .12       0
  3607.7     .07       0  3737.8     .05       0  4337.7     .07       0
  4583.1     .05       0    4905    .035       0  5086.4    .035       0
  5175.7     .05       0  5507.7     .07       0  5613.2     .12       0
  5820.7     .05       0  5925.1     .08       0  6063.3     .12       0
  6490.3     .08       0  6655.9     .07       0  6969.1     .05       0
  7378.5     .12       0
Bank Sta=4905,5086.4
XS Rating Curve= 0 ,0
Exp/Cntr=0.3,0.1

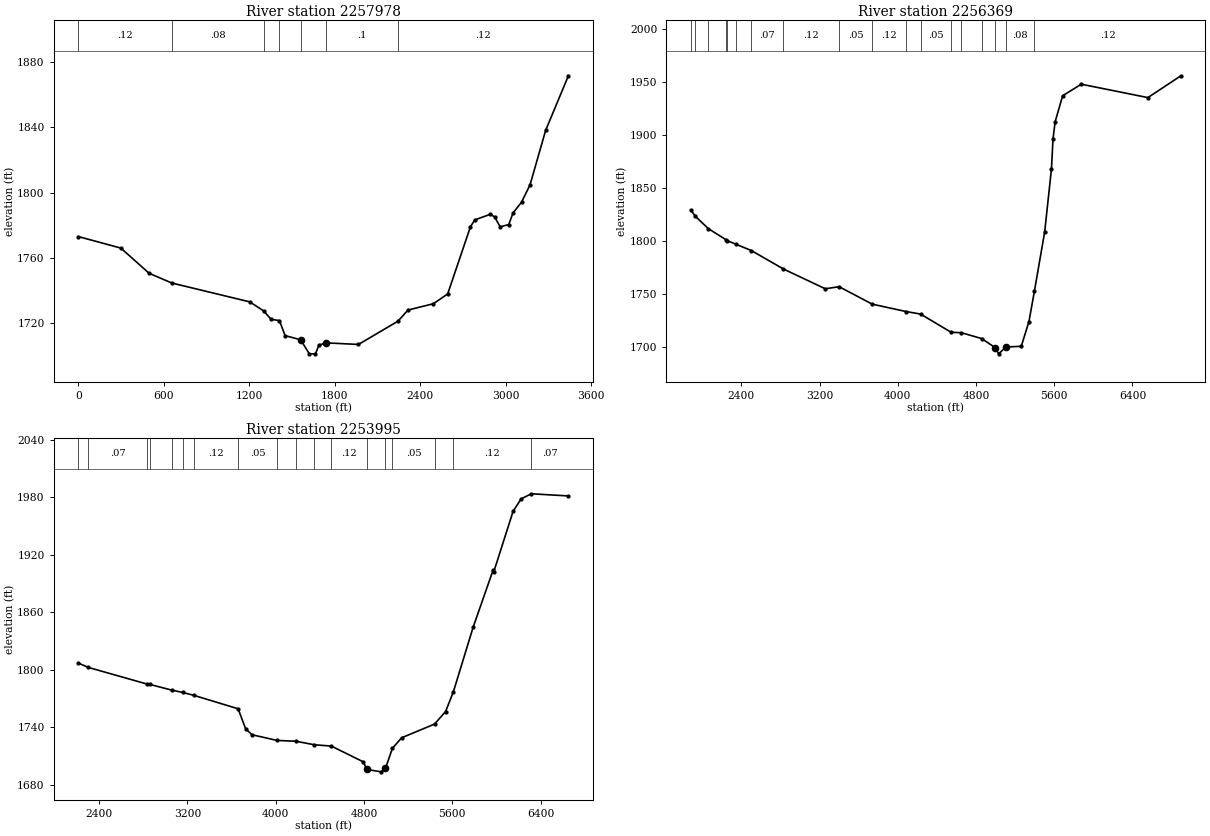
Type RM Length L Ch R = 1 ,2257978 ,1609,1609,1609
XS GIS Cut Line= 4
  1876260.80934313937437.3162396  1876405.14173213936063.0214161
 1875564.249056813935874.7619501 1874924.166675613934864.4355586
#Sta/Elev= 30
       0 1772.94  298.24 1765.87  497.07 1750.37  656.13 1744.41 1202.91 1732.84
 1302.32  1727.2 1352.03 1722.16 1411.57 1721.34 1451.19 1712.11 1560.14 1709.57
 1621.09 1700.92 1664.06 1700.92  1688.9 1706.29 1738.42 1707.66 1966.23 1706.69
 2243.56 1720.98 2313.33  1727.8 2492.73 1731.72  2592.4 1737.74 2751.87 1778.91
 2781.77 1783.15 2891.41 1786.63 2921.31 1785.06 2961.18 1778.92 3020.98 1780.33
 3050.88 1787.43 3110.68 1794.07 3170.48 1804.74 3280.12 1838.24 3439.59  1871.7
#Mann= 7 ,-1 , 0
       0     .12       0  656.13     .08       0 1302.32     .05       0
 1411.57      .1       0 1560.14     .04       0 1738.42      .1       0
 2243.56     .12       0
Bank Sta=1560.14,1738.42
XS Rating Curve= 0 ,0
Exp/Cntr=0.3,0.1

Type RM Length L Ch R = 1 ,2256369 ,2374,2374,2374
BEGIN DESCRIPTION:
Guadalupe River - 179
END DESCRIPTION:
XS GIS Cut Line= 3
      1875946.29     13938422.12      1877356.87     13934754.61
      1878267.26     13934169.36
#Sta/Elev= 30
  1883.5 1829.14  1929.2  1823.2  2061.3 1811.64  2246.5  1800.9  2253.8 1800.33
  2349.8 1796.67  2501.6 1790.94  2829.2 1773.56    3258 1754.88  3400.2 1756.82
  3738.4 1740.37  4084.4 1733.42  4232.9 1731.02  4545.2 1713.85  4649.2 1713.47
  4857.4 1707.92  4998.2 1699.24  5031.2 1693.53  5105.4 1699.98  5262.6 1700.64
  5341.1 1723.97  5397.8 1753.12  5501.8 1808.38  5571.2 1867.86  5587.5 1896.43
  5608.9 1912.36  5685.8 1936.88  5876.5 1947.76  6557.4 1935.14  6895.2 1955.71
#Mann= 18 ,-1 , 0
  1883.5     .12       0  1929.2     .05       0  2061.3     .12       0
  2246.5     .05       0  2253.8     .12       0  2349.8     .05       0
  2501.6     .07       0  2829.2     .12       0  3400.2     .05       0
  3738.4     .12       0  4084.4     .07       0  4232.9     .05       0
  4545.2     .12       0  4649.2     .05       0  4857.4     .08       0
  4998.2     .04       0  5105.4     .08       0  5397.8     .12       0
Bank Sta=4998.2,5105.4
XS Rating Curve= 0 ,0
Exp/Cntr=0.3,0.1

Type RM Length L Ch R = 1 ,2253995 ,3258,3258,3258
BEGIN DESCRIPTION:
Guadalupe River - 178
END DESCRIPTION:
XS GIS Cut Line= 6
      1878007.92     13938769.32      1878399.53     13937112.03
      1878851.87     13936249.67      1878972.78     13936019.22
      1879112.47     13935752.89      1879244.86     13934559.62
#Sta/Elev= 30
  2212.9 1807.07  2303.8 1802.54  2834.7 1785.22  2857.7 1784.92  3058.3 1778.92
  3158.6 1776.44  3258.9 1773.46  3660.1 1759.44  3727.8 1738.61  3785.9 1732.39
  4012.5 1726.47  4183.5 1725.62  4351.6 1721.92  4503.8  1720.6  4793.3 1704.17
  4825.4 1696.28  4954.1 1693.74  4994.6  1697.4  5057.2 1718.23  5140.8 1729.23
    5439 1743.52    5539 1756.59  5609.6  1777.2  5788.2 1844.33  5969.5 1904.08
  5974.5 1901.88  6150.7 1965.35  6223.2  1978.2  6315.5 1983.51  6651.2 1981.26
#Mann= 18 ,-1 , 0
  2212.9     .05       0  2303.8     .07       0  2834.7     .05       0
  2857.7     .07       0  3058.3     .12       0  3158.6     .07       0
  3258.9     .12       0  3660.1     .05       0  4012.5     .08       0
  4183.5     .12       0  4351.6     .05       0  4503.8     .12       0
  4825.4     .04       0  4994.6     .12       0  5057.2     .05       0
    5439     .07       0  5609.6     .12       0  6315.5     .07       0
Bank Sta=4825.4,4994.6
XS Rating Curve= 0 ,0
Exp/Cntr=0.3,0.1