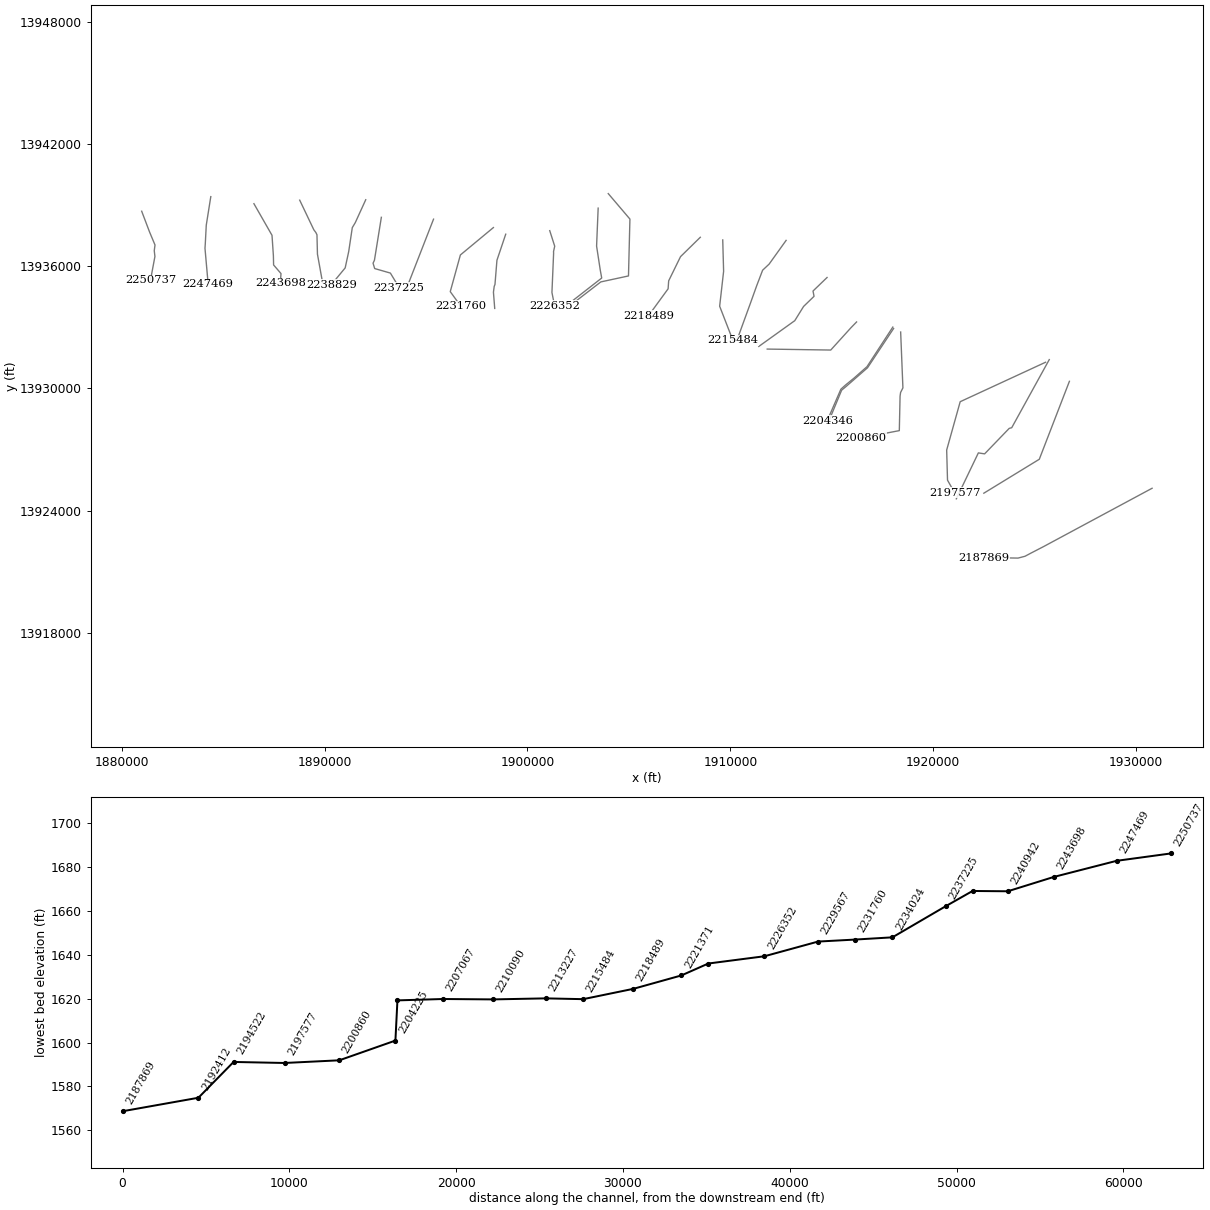
HEC-RAS study Guadalupe River.prj: Guadalupe River Base Level Engineering

--- Guadalupe River.g01 (geometry) --- (continued)

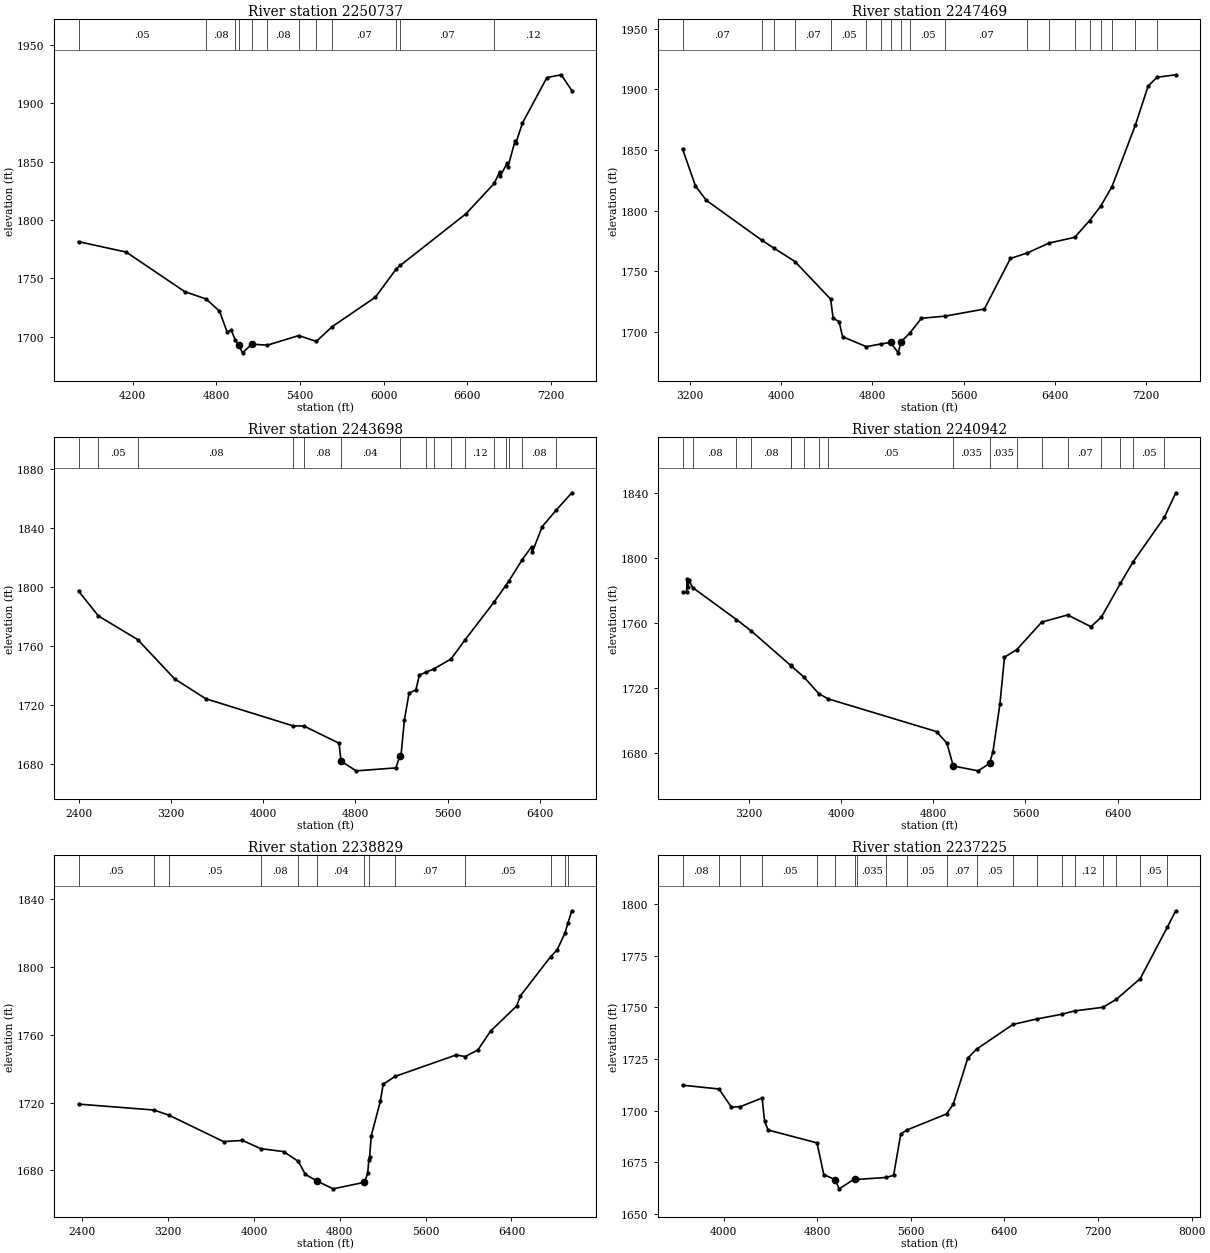
Type RM Length L Ch R = 1 ,2250737 ,3268,3268,3268
BEGIN DESCRIPTION:
Guadalupe River - 177
END DESCRIPTION:
XS GIS Cut Line= 6
      1880981.01     13938704.25      1881370.33      13937680.8
      1881637.67     13937045.65      1881600.53     13936765.35
      1881633.65      13936481.3      1881415.14     13935319.41
#Sta/Elev= 30
  3812.8 1781.49  4154.4 1772.57  4573.2 1738.75  4727.5 1732.37  4822.8    1722
  4877.7 1704.15  4907.3 1705.65  4935.7 1697.34  4960.7 1693.02    4988 1686.28
  5055.1 1693.73  5165.9 1692.83  5390.8 1701.07  5516.9 1696.07  5630.8 1708.71
  5940.4 1733.93  6091.4 1758.37  6119.3 1761.18  6589.2 1805.33    6792 1831.37
  6831.5 1841.33  6836.6 1837.89    6884 1848.69  6889.1 1845.09  6941.6 1867.85
  6946.7 1865.78  6994.1 1883.02  7169.2 1921.97  7271.8 1924.39  7347.9 1910.91
#Mann= 12 ,-1 , 0
  3812.8     .05       0  4727.5     .08       0  4935.7     .12       0
  4960.7     .04       0  5055.1     .12       0  5165.9     .08       0
  5390.8     .07       0  5516.9     .05       0  5630.8     .07       0
  6091.4     .12       0  6119.3     .07       0    6792     .12       0
Bank Sta=4960.7,5055.1
XS Rating Curve= 0 ,0
Exp/Cntr=0.3,0.1

Type RM Length L Ch R = 1 ,2247469 ,3771,3771,3771
BEGIN DESCRIPTION:
Guadalupe River - 176
END DESCRIPTION:
XS GIS Cut Line= 6
      1884388.11     13939420.36      1884165.12     13938020.68
      1884127.34      13937308.2       1884114.8     13937071.18
      1884101.65     13936883.38      1884257.91     13935123.53
#Sta/Elev= 30
  3136.8 1850.95  3250.2 1820.46  3344.8  1808.6  3834.5 1775.52  3934.6 1769.39
  4122.2 1758.13  4435.1 1727.14  4456.6 1711.59  4509.3 1708.55  4539.6 1696.19
  4747.3    1688  4873.6 1690.18  4960.4 1691.49  5027.6  1682.9  5050.5 1691.83
  5127.4 1699.04  5230.8 1711.38    5439 1713.15    5782 1718.98  6010.8 1760.66
    6159 1765.22  6350.3 1773.38  6573.8 1778.05  6704.2 1791.83  6802.6 1803.85
  6901.1 1819.91  7106.1 1870.66  7217.6 1902.72  7294.9 1909.94    7460    1912
#Mann= 19 ,-1 , 0
  3136.8     .07       0  3834.5     .05       0  3934.6     .12       0
  4122.2     .07       0  4435.1     .05       0  4747.3    .035       0
  4873.6     .12       0  4960.4     .04       0  5050.5     .12       0
  5127.4     .05       0    5439     .07       0    6159     .05       0
  6350.3     .12       0  6573.8     .05       0  6704.2     .12       0
  6802.6     .05       0  6901.1     .12       0  7106.1     .05       0
  7294.9     .08       0
Bank Sta=4960.4,5050.5
XS Rating Curve= 0 ,0
Exp/Cntr=0.3,0.1

Type RM Length L Ch R = 1 ,2243698 ,2756,2756,2756
BEGIN DESCRIPTION:
Guadalupe River - 175
END DESCRIPTION:
XS GIS Cut Line= 6
      1886514.86     13939073.18       1887405.8     13937521.73
      1887474.02     13936518.04      1887484.16     13936064.91
      1887848.66     13935642.84      1887817.04     13935168.42
#Sta/Elev= 30
  2395.5 1797.55  2568.2 1780.61  2910.1 1764.53  3229.3 1737.95  3500.4 1724.45
  4259.5 1706.02  4351.5 1705.98  4657.9 1694.23  4673.9 1682.12  4805.9 1675.54
  5150.5 1677.54  5184.7 1685.48  5195.7 1686.28  5224.8 1710.15  5264.8 1728.06
  5324.8 1730.58  5354.8 1740.54  5411.2 1742.42  5477.5 1744.55  5629.7 1751.45
  5751.8 1764.45  6004.7 1790.21    6104 1801.18  6131.2 1804.25  6245.6 1818.57
  6329.3 1827.63  6334.3 1823.81    6421 1841.23  6541.9 1852.35  6678.1 1864.18
#Mann= 16 ,-1 , 0
  2395.5     .08       0  2568.2     .05       0  2910.1     .08       0
  4259.5     .05       0  4351.5     .08       0  4673.9     .04       0
  5184.7     .08       0  5411.2     .07       0  5477.5     .05       0
  5629.7     .07       0  5751.8     .12       0  6004.7     .05       0
    6104     .12       0  6131.2     .05       0  6245.6     .08       0
  6541.9     .05       0
Bank Sta=4673.9,5184.7
XS Rating Curve= 0 ,0
Exp/Cntr=0.3,0.1

Type RM Length L Ch R = 1 ,2240942 ,2113,2113,2113
BEGIN DESCRIPTION:
Guadalupe River - 174
END DESCRIPTION:
XS GIS Cut Line= 6
       1888771.8      13939246.8      1889468.43      13937790.2
      1889567.14     13937659.83      1889622.41     13937546.52
      1889646.16     13936595.87      1889900.01     13935190.09
#Sta/Elev= 30
  2622.2 1779.31  2657.4  1779.5  2663.7 1787.49  2669.2 1782.18  2679.6 1786.38
  2709.7 1782.02  3090.8 1762.29  3216.9  1755.4  3560.8 1734.06  3564.8 1733.78
  3679.1 1726.65  3805.8 1716.59  3886.9 1713.39    4828 1693.22  4918.1 1686.06
  4973.3    1672  5189.4 1669.01  5288.2 1673.57  5318.2  1680.8  5378.5 1710.19
  5418.3 1739.08  5525.4 1743.77  5741.5  1760.7    5967 1765.12  6169.2 1757.88
  6260.6 1763.88  6425.4 1784.66    6534 1797.73  6806.4 1825.28  6905.9 1840.44
#Mann= 18 ,-1 , 0
  2622.2     .05       0  2709.7     .08       0  3090.8     .05       0
  3216.9     .08       0  3560.8     .05       0  3564.8     .08       0
  3679.1     .05       0  3805.8     .08       0  3886.9     .05       0
  4973.3    .035       0  5288.2    .035       0  5525.4     .07       0
  5741.5     .12       0    5967     .07       0  6260.6     .05       0
  6425.4     .07       0    6534     .05       0  6806.4     .07       0
Bank Sta=4973.3,5288.2
XS Rating Curve= 0 ,0
Exp/Cntr=0.3,0.1

Type RM Length L Ch R = 1 ,2238829 ,1604,1604,1604
BEGIN DESCRIPTION:
Guadalupe River - 173
END DESCRIPTION:
XS GIS Cut Line= 6
      1892027.02     13939268.52      1891512.17     13938145.72
      1891363.88     13937898.07      1891187.76      13936725.9
      1891013.05     13935920.02      1890334.29     13935101.81
#Sta/Elev= 30
  2365.5  1719.1  3068.4 1715.61  3211.5 1712.49    3717 1696.99  3893.4 1697.68
  4063.6 1692.84  4276.7  1691.1  4414.2 1685.32    4479 1677.68  4586.9 1673.77
    4739 1669.14  5030.3 1673.01    5060 1678.25  5070.8 1686.25  5077.7 1687.66
  5093.5 1700.42  5177.9 1720.71  5204.6 1730.77    5314 1735.38    5884 1748.07
  5970.1 1747.15  6086.6 1751.01  6206.4 1762.21  6448.6 1776.97  6483.8 1782.97
  6765.4 1806.05    6825 1809.97  6897.9 1819.81  6925.2 1825.65  6962.4 1833.09
#Mann= 13 ,-1 , 0
  2365.5     .05       0  3068.4     .08       0  3211.5     .05       0
  4063.6     .08       0  4414.2     .12       0  4586.9     .04       0
  5030.3     .12       0  5070.8     .12       0    5314     .07       0
  5970.1     .05       0  6765.4     .07       0  6897.9     .05       0
  6925.2     .07       0
Bank Sta=4586.9,5030.3
XS Rating Curve= 0 ,0
Exp/Cntr=0.3,0.1

Type RM Length L Ch R = 1 ,2237225 ,3201,3201,3201
BEGIN DESCRIPTION:
Guadalupe River - 172
END DESCRIPTION:
XS GIS Cut Line= 6
      1892796.58     13938404.76       1892456.3     13936297.36
      1892387.48     13936152.29      1892467.76     13935888.04
      1893242.29     13935666.07      1893676.27       13934950.
#Sta/Elev= 30
  3649.6 1712.34  3961.3 1710.52  4067.4 1701.71    4145 1701.99  4329.5 1706.18
  4351.2 1694.85  4381.6 1690.66  4798.8 1684.44  4856.8 1669.11  4951.9 1666.73
  4988.8 1662.22  5119.7 1667.07  5144.3 1666.78  5389.7 1667.72  5453.4 1668.75
  5514.1 1688.67  5564.3 1690.62  5906.1 1698.45  5963.4 1703.19  6087.6 1725.44
    6163 1729.82  6473.9 1741.75  6679.4  1744.4    6888 1746.65  7000.5 1748.29
  7243.5 1750.04  7356.3 1753.88  7560.5 1763.86  7792.7 1788.85  7864.5 1796.71
#Mann= 20 ,-1 , 0
  3649.6     .08       0  3961.3     .05       0    4145     .08       0
  4329.5     .05       0  4798.8     .07       0  4951.9     .04       0
  5119.7     .07       0  5144.3    .035       0  5389.7     .12       0
  5564.3     .05       0  5906.1     .07       0    6163     .05       0
  6473.9     .05       0  6679.4     .07       0    6888     .05       0
  7000.5     .12       0  7243.5     .12       0  7356.3     .05       0
  7560.5     .05       0  7792.7     .12       0
Bank Sta=4951.9,5119.7
XS Rating Curve= 0 ,0
Exp/Cntr=0.3,0.1

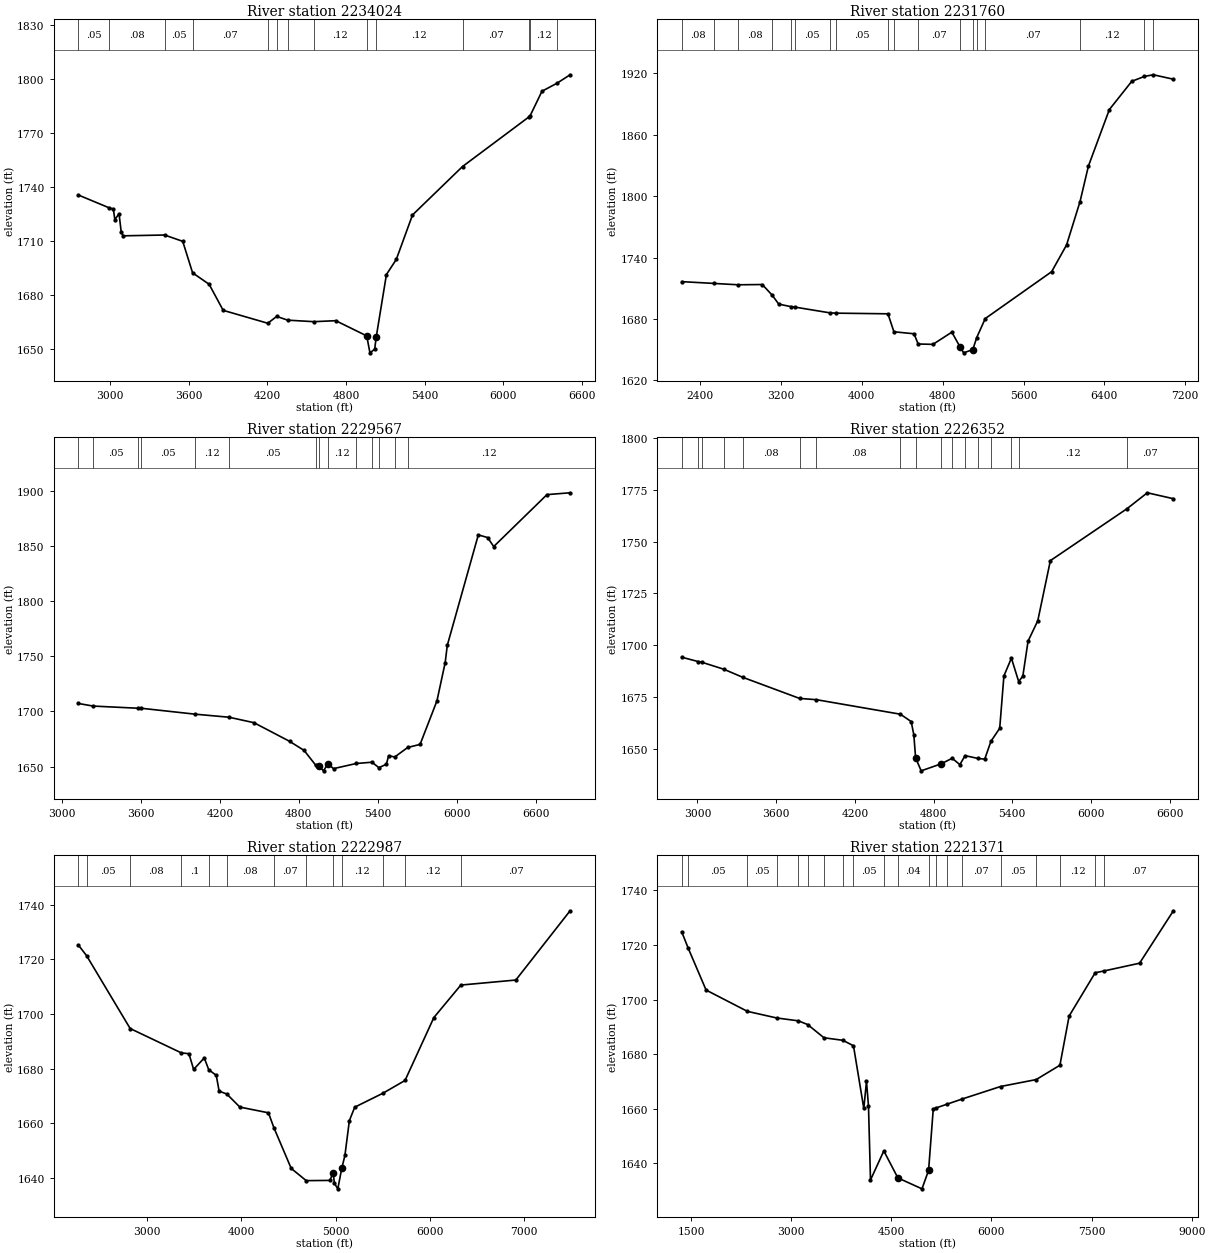
Type RM Length L Ch R = 1 ,2234024 ,2264,2264,2264
BEGIN DESCRIPTION:
Guadalupe River - 171
END DESCRIPTION:
XS GIS Cut Line= 2
      1895369.01      13938313.6      1894001.89     13934819.85
#Sta/Elev= 30
  2757.7 1735.69  2989.2 1728.68  3024.3 1727.89  3035.4 1722.04  3067.6 1725.31
    3084 1715.22  3099.8 1713.03  3414.9 1713.48  3553.5 1709.97  3628.8 1692.46
  3754.9 1686.11  3862.2 1671.62  4202.7 1664.44  4270.5 1668.24  4354.8 1666.16
  4554.4 1665.32  4721.3 1665.87  4957.6 1657.41  4982.1    1648  5018.2    1650
    5030 1656.78  5107.9 1691.52  5183.1  1699.9  5306.8 1724.62  5688.5 1751.54
  6195.6 1779.12  6202.9 1779.53  6294.8 1793.38  6409.5 1797.84  6509.4 1802.53
#Mann= 14 ,-1 , 0
  2757.7     .05       0  2989.2     .08       0  3414.9     .05       0
  3628.8     .07       0  4202.7    .035       0  4270.5     .12       0
  4354.8     .07       0  4554.4     .12       0  4957.6     .04       0
    5030     .12       0  5688.5     .07       0  6195.6     .05       0
  6202.9     .12       0  6409.5     .07       0
Bank Sta=4957.6,5030
XS Rating Curve= 0 ,0
Exp/Cntr=0.3,0.1

Type RM Length L Ch R = 1 ,2231760 ,2193,2193,2193
BEGIN DESCRIPTION:
Guadalupe River - 170
END DESCRIPTION:
XS GIS Cut Line= 4
      1898320.44     13937901.33      1896692.81     13936555.82
      1896193.68     13934754.61      1896713.93     13934039.25
#Sta/Elev= 30
  2217.5 1716.47  2537.8 1714.72  2774.7  1713.4  3014.8 1713.65  3113.1  1703.2
  3177.6 1694.54  3296.3  1692.1  3334.6 1691.66  3682.6 1686.02  3745.3 1685.71
  4258.3 1685.07  4317.3 1667.53  4516.9 1665.57  4556.9  1655.6  4703.7 1655.25
  4890.5 1667.14  4972.3 1652.64  5007.5 1646.97    5098 1650.11  5136.8 1661.85
  5221.1 1680.43  5878.3 1726.18  6025.8 1752.27  6159.2 1794.62  6242.1 1829.28
  6449.3 1884.44    6671 1911.99  6797.1 1916.83    6885 1918.39  7082.9 1914.05
#Mann= 18 ,-1 , 0
  2217.5     .08       0  2537.8     .05       0  2774.7     .08       0
  3113.1     .05       0  3296.3     .08       0  3334.6     .05       0
  3682.6     .08       0  3745.3     .05       0  4258.3     .08       0
  4317.3     .05       0  4556.9     .07       0  4972.3     .04       0
    5098     .07       0  5136.8     .12       0  5221.1     .07       0
  6159.2     .12       0  6797.1     .07       0    6885     .12       0
Bank Sta=4972.3,5098
XS Rating Curve= 0 ,0
Exp/Cntr=0.3,0.1

Type RM Length L Ch R = 1 ,2229567 ,3215,3215,3215
BEGIN DESCRIPTION:
Guadalupe River - 169
END DESCRIPTION:
XS GIS Cut Line= 6
      1898928.05     13937575.78      1898495.12     13936295.38
      1898397.81     13935103.14      1898360.72     13935015.79
      1898322.63     13934726.27      1898385.51     13933930.02
#Sta/Elev= 30
  3125.9 1707.16  3238.2 1704.81  3581.3 1702.84  3604.7 1702.81  4010.9 1697.48
  4269.6  1694.7  4458.9 1689.75  4729.6 1672.84  4839.9 1664.58    4929 1651.06
  4950.3 1650.56  4987.5 1646.07  5020.5 1652.49  5063.4 1648.07  5236.1 1652.73
  5355.8 1653.89  5407.9 1648.94  5464.7 1652.03  5482.1 1659.81    5528 1658.61
  5626.9 1667.27  5720.8 1670.05  5848.8 1709.49  5911.5 1744.28  5927.4 1759.88
  6163.1 1860.08  6233.3  1857.7  6280.2 1849.53  6684.7 1896.62  6860.2 1898.28
#Mann= 14 ,-1 , 0
  3125.9     .08       0  3238.2     .05       0  3581.3     .08       0
  3604.7     .05       0  4010.9     .12       0  4269.6     .05       0
    4929     .12       0  4950.3     .04       0  5020.5     .12       0
  5236.1     .05       0  5355.8     .07       0  5407.9     .05       0
    5528     .07       0  5626.9     .12       0
Bank Sta=4950.3,5020.5
XS Rating Curve= 0 ,0
Exp/Cntr=0.3,0.1

Type RM Length L Ch R = 1 ,2226352 ,3365,3365,3365
BEGIN DESCRIPTION:
Guadalupe River - 168
END DESCRIPTION:
XS GIS Cut Line= 6
      1901098.21     13937749.35      1901342.99     13936986.15
      1901284.38     13936716.49       1901289.3     13936647.89
      1901206.67      13934711.9       1901336.9     13934060.19
#Sta/Elev= 30
  2880.2 1694.21  3005.8 1692.11  3032.7  1691.8    3201 1688.41  3345.2 1684.52
  3778.7 1674.32  3907.1 1673.71  4547.6  1666.7  4629.9 1663.14  4649.9 1656.73
  4663.5 1645.63  4705.9 1639.37  4859.8 1642.79    4942 1645.44  5001.1 1642.36
  5040.6 1646.71  5139.2 1645.35  5190.5 1645.02  5237.8 1653.62  5304.7 1659.91
  5336.7 1685.18  5393.9 1693.76  5449.2 1682.48  5480.8 1685.02  5520.8 1701.96
  5594.9  1711.8  5690.9 1740.82  6274.7 1765.86  6430.1 1773.57  6628.8 1770.71
#Mann= 17 ,-1 , 0
  2880.2     .08       0  3005.8      .1       0  3032.7     .08       0
    3201     .05       0  3345.2     .08       0  3778.7     .07       0
  3907.1     .08       0  4547.6     .05       0  4663.5    .035       0
  4859.8     .05       0    4942     .07       0  5040.6     .12       0
  5139.2     .07       0  5237.8     .12       0  5393.9     .05       0
  5449.2     .12       0  6274.7     .07       0
Bank Sta=4663.5,4859.8
XS Rating Curve= 0 ,0
Exp/Cntr=0.3,0.1

Type RM Length L Ch R = 1 ,2222987 ,1616,1616,1616
BEGIN DESCRIPTION:
Guadalupe River - 167
END DESCRIPTION:
XS GIS Cut Line= 6
      1903485.34     13938856.15      1903407.84     13936991.49
      1903499.96     13936392.81      1903589.41     13935811.24
      1903660.27     13935422.16      1902270.09      13934342.3
#Sta/Elev= 30
    2271 1725.18  2356.7 1721.38  2819.8 1694.69    3363 1685.78  3443.2 1685.49
  3493.2 1679.74    3606 1683.93  3653.6 1679.63  3733.4 1677.56  3763.4  1671.8
  3845.6 1670.73  3983.6 1665.96  4286.8 1663.87  4344.5 1658.44  4528.3 1643.53
  4687.6 1639.06  4939.3 1639.14  4973.5 1642.03  4986.5 1638.06  5022.8 1636.06
  5064.5 1643.53  5098.2 1648.27  5145.5 1661.02  5202.4 1665.93  5502.1 1671.04
    5736  1675.7    6042 1698.72  6328.1 1710.59  6911.2 1712.43  7487.2 1737.76
#Mann= 13 ,-1 , 0
    2271     .08       0  2356.7     .05       0  2819.8     .08       0
    3363      .1       0  3653.6     .05       0  3845.6     .08       0
  4344.5     .07       0  4687.6    .035       0  4973.5     .04       0
  5064.5     .12       0  5502.1     .07       0    5736     .12       0
  6328.1     .07       0
Bank Sta=4973.5,5064.5
XS Rating Curve= 0 ,0
Exp/Cntr=0.3,0.1

Type RM Length L Ch R = 1 ,2221371 ,2882,2882,2882
BEGIN DESCRIPTION:
Guadalupe River - 166
END DESCRIPTION:
XS GIS Cut Line= 5
      1903983.54     13939568.46      1905051.24     13938318.47
      1904980.14     13935525.36      1903615.55     13935232.04
        1902401.     13934299.43
#Sta/Elev= 30
  1361.4 1724.84  1457.6 1718.89  1726.5 1703.49  2345.3 1695.68  2781.4 1693.27
  3108.9  1692.2  3247.5 1690.85  3492.4    1686  3774.8 1685.07  3934.2 1683.07
  4089.1 1660.08  4129.2 1670.05  4159.2    1661  4189.2 1633.87  4388.9 1644.52
  4599.3 1634.63  4960.4 1630.62  5059.5  1637.4  5129.5 1659.92  5176.6 1660.32
  5335.7 1661.65    5560 1663.53  6137.1 1668.13  6671.1 1670.67  7026.7 1675.93
    7165 1693.98    7555 1709.83  7684.7 1710.48  8219.9 1713.33  8726.4 1732.55
#Mann= 20 ,-1 , 0
  1361.4     .07       0  1457.6     .05       0  2345.3     .05       0
  2781.4     .08       0  3108.9      .1       0  3247.5      .1       0
  3492.4      .1       0  3774.8     .08       0  3934.2     .05       0
  4388.9     .07       0  4599.3     .04       0  5059.5     .07       0
  5176.6     .07       0  5335.7     .05       0    5560     .07       0
  6137.1     .05       0  6671.1     .07       0  7026.7     .12       0
    7555     .05       0  7684.7     .07       0
Bank Sta=4599.3,5059.5
XS Rating Curve= 0 ,0
Exp/Cntr=0.3,0.1

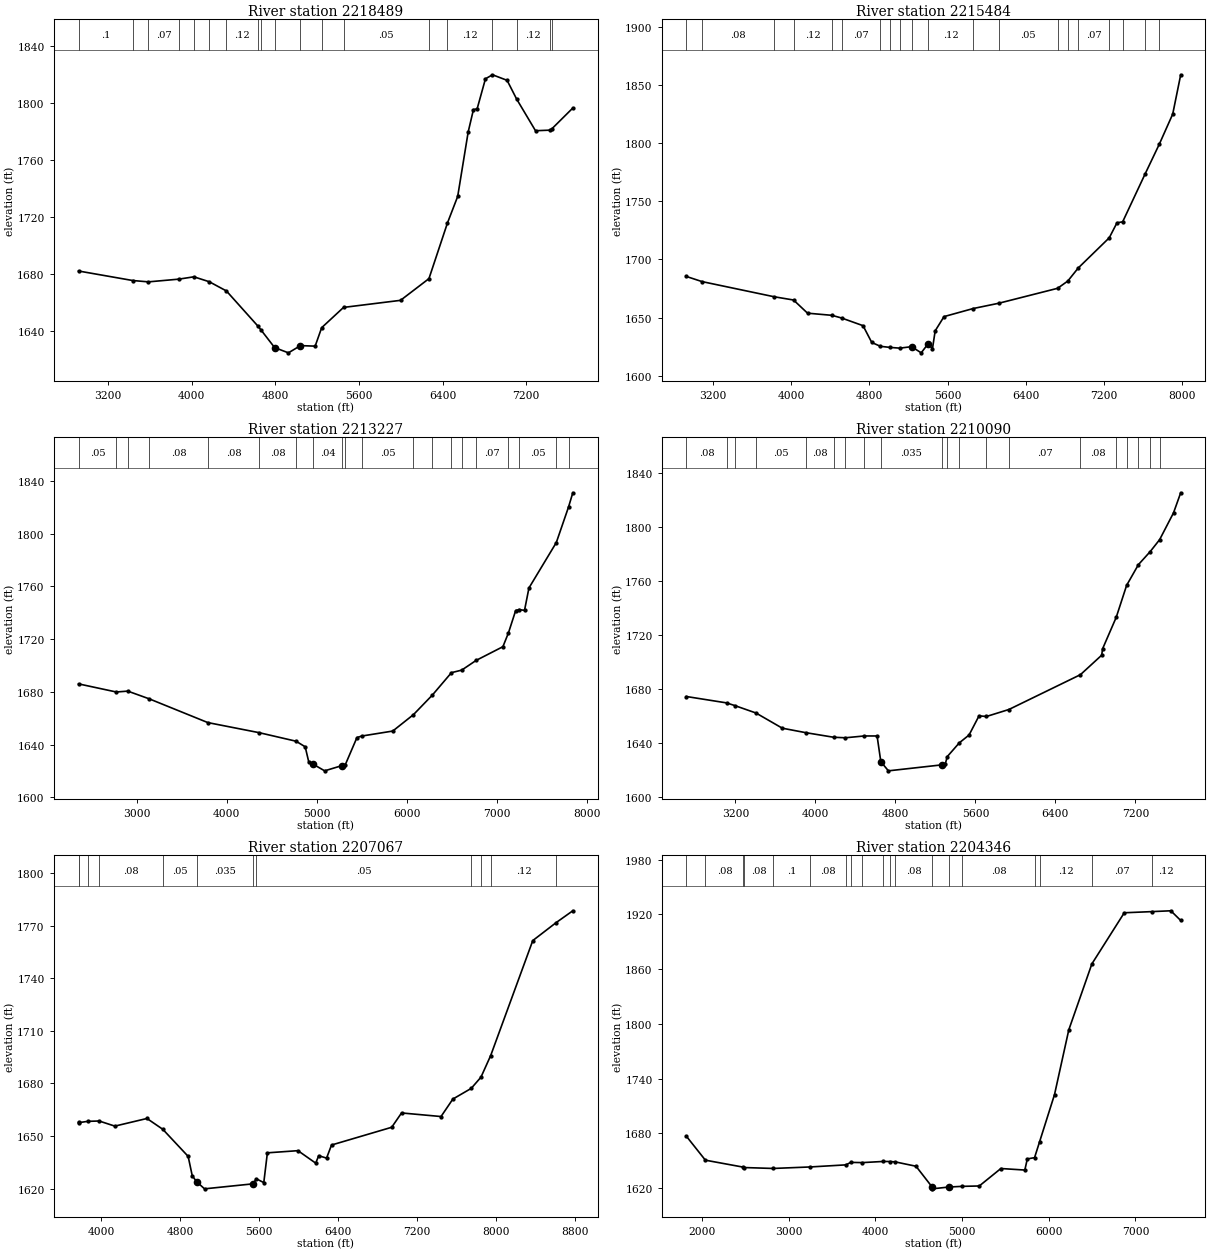
Type RM Length L Ch R = 1 ,2218489 ,3005,3005,3005
BEGIN DESCRIPTION:
Guadalupe River - 165
END DESCRIPTION:
XS GIS Cut Line= 6
      1908520.03     13937423.85      1907550.14     13936477.12
      1907543.12      13936467.8      1906961.79     13935284.91
      1906933.93     13934893.53      1905959.66     13933561.53
#Sta/Elev= 30
  2917.1 1682.03  3435.4 1675.34  3585.1  1674.4  3876.8 1676.32  4020.1 1677.95
  4167.3 1674.49  4331.4 1668.01  4634.5 1643.16  4665.1 1640.32  4792.8 1628.18
  4924.4 1624.51  5039.9  1629.6  5180.2 1629.21  5242.5 1642.19  5451.7 1656.44
  5996.7 1661.41  6268.7 1676.67  6445.9 1715.82  6543.6 1734.45    6644 1779.76
  6694.2 1795.48  6729.7 1796.03  6809.2 1817.15  6876.6 1819.97  7016.2 1816.07
  7106.7    1803    7288 1780.64  7429.5 1781.06    7444 1781.95  7644.8 1796.59
#Mann= 19 ,-1 , 0
  2917.1      .1       0  3435.4     .05       0  3585.1     .07       0
  3876.8     .05       0  4020.1     .08       0  4167.3     .05       0
  4331.4     .12       0  4634.5     .07       0  4665.1     .12       0
  4792.8    .035       0  5039.9     .07       0  5242.5     .07       0
  5451.7     .05       0  6268.7     .07       0  6445.9     .12       0
  6876.6     .07       0  7106.7     .12       0  7429.5     .07       0
    7444     .12       0
Bank Sta=4792.8,5039.9
XS Rating Curve= 0 ,0
Exp/Cntr=0.3,0.1

Type RM Length L Ch R = 1 ,2215484 ,2257,2257,2257
BEGIN DESCRIPTION:
Guadalupe River - 164
END DESCRIPTION:
XS GIS Cut Line= 4
      1909626.84      13937293.7      1909670.24     13935752.87
      1909474.93     13934038.46      1910125.46     13932368.75
#Sta/Elev= 30
  2926.9 1685.39  3086.6 1680.99  3826.3 1667.94  4022.9 1665.18  4166.1 1653.87
  4416.1 1652.02  4514.9 1649.72  4734.2 1643.13  4823.7 1628.69  4912.3  1625.4
  5011.6 1624.46    5111 1623.83  5230.8 1625.09  5329.6  1619.8  5400.1 1627.56
  5444.9 1623.36  5472.7  1638.7  5563.2 1650.93  5862.7 1657.88    6122 1662.37
  6725.6 1675.23  6829.9 1681.45  6937.5 1692.73  7254.3  1718.6  7333.5  1731.5
  7391.6 1732.34  7620.6 1773.31  7768.2  1799.3    7904 1824.87  7985.8 1858.65
#Mann= 20 ,-1 , 0
  2926.9     .05       0  3086.6     .08       0  3826.3     .05       0
  4022.9     .12       0  4416.1     .05       0  4514.9     .07       0
  4912.3     .07       0  5011.6     .08       0    5111     .05       0
  5230.8     .04       0  5400.1     .12       0  5862.7     .05       0
    6122     .05       0  6725.6     .05       0  6829.9     .07       0
  6937.5     .07       0  7254.3     .05       0  7391.6     .08       0
  7620.6     .05       0  7768.2     .07       0
Bank Sta=5230.8,5400.1
XS Rating Curve= 0 ,0
Exp/Cntr=0.3,0.1

Type RM Length L Ch R = 1 ,2213227 ,3137,3137,3137
BEGIN DESCRIPTION:
Guadalupe River - 163
END DESCRIPTION:
XS GIS Cut Line= 6
      1912751.81     13937271.94      1911913.11     13936105.88
      1911593.01     13935806.72       1911297.6     13935035.11
      1910988.82     13934176.58      1910342.99     13932410.87
#Sta/Elev= 30
  2353.4 1686.11  2772.5 1679.96  2900.5 1680.62  3141.2  1674.7  3789.9 1656.76
  4361.1  1649.1  4770.8 1642.62  4872.2 1638.39  4912.6  1626.7  4957.9 1625.31
  5088.3 1620.16  5283.1 1624.17  5317.2 1624.68  5447.4  1645.4  5501.6 1646.56
  5845.4 1650.33  6075.4 1662.78  6285.9 1677.64  6497.8 1694.62  6611.9 1696.55
  6772.7 1703.94  7069.8 1714.32  7131.3 1724.79  7211.7 1741.75  7250.6 1742.49
  7309.8 1741.83  7359.1 1758.86  7663.3 1793.31  7799.4 1820.31  7846.6 1831.05
#Mann= 20 ,-1 , 0
  2353.4     .05       0  2772.5     .08       0  2900.5     .05       0
  3141.2     .08       0  3789.9     .08       0  4361.1     .08       0
  4770.8     .05       0  4957.9     .04       0  5283.1     .05       0
  5317.2     .07       0  5501.6     .05       0  6075.4     .07       0
  6285.9     .08       0  6497.8     .05       0  6611.9     .08       0
  6772.7     .07       0  7131.3     .05       0  7250.6     .05       0
  7663.3     .05       0  7799.4     .07       0
Bank Sta=4957.9,5283.1
XS Rating Curve= 0 ,0
Exp/Cntr=0.3,0.1

Type RM Length L Ch R = 1 ,2210090 ,3023,3023,3023
BEGIN DESCRIPTION:
Guadalupe River - 162
END DESCRIPTION:
XS GIS Cut Line= 6
      1914770.06     13935449.05       1914077.4     13934784.31
      1914128.34     13934524.28      1913614.17      13934028.4
      1913178.48     13933328.74      1911406.37     13932063.65
#Sta/Elev= 30
  2711.3  1674.6  3112.1  1669.9  3192.9 1667.96  3405.9 1662.44  3669.5  1651.2
  3901.6 1647.93  4183.5  1644.5  4300.4 1644.12  4488.8 1645.46  4617.3 1645.46
  4654.7 1626.45  4730.4 1619.69  5262.6 1624.09  5299.2 1624.91  5319.7 1630.27
  5439.6  1640.4  5536.7 1646.14  5636.5 1660.32  5710.9 1659.86  5934.9 1665.01
  6650.4 1690.74  6863.1 1705.15  6871.8 1709.85  7008.2 1733.11  7112.3 1756.75
  7230.2 1772.06  7348.1  1781.7  7442.4 1790.53  7581.3 1810.35    7653 1825.15
#Mann= 20 ,-1 , 0
  2711.3     .08       0  3112.1     .05       0  3192.9     .08       0
  3405.9     .05       0  3901.6     .08       0  4183.5     .08       0
  4300.4      .1       0  4488.8     .08       0  4654.7    .035       0
  5262.6     .08       0  5319.7     .05       0  5439.6     .05       0
  5710.9     .07       0  5934.9     .07       0  6650.4     .08       0
  7008.2     .05       0  7112.3     .12       0  7230.2     .07       0
  7348.1     .05       0  7442.4     .12       0
Bank Sta=4654.7,5262.6
XS Rating Curve= 0 ,0
Exp/Cntr=0.3,0.1

Type RM Length L Ch R = 1 ,2207067 ,2721,2721,2721
BEGIN DESCRIPTION:
Guadalupe River - 161
END DESCRIPTION:
XS GIS Cut Line= 6
      1916225.03     13933265.06       1915947.6      13932980.7
      1915666.36     13932671.56       1915031.5     13931973.65
      1914951.48     13931885.72       1911819.3     13931933.42
#Sta/Elev= 30
  3769.2 1657.98  3776.4 1657.68  3862.4 1658.39  3977.7 1658.58    4137 1655.66
  4462.5 1660.02  4623.1 1653.84  4880.1 1638.39  4921.3 1627.41  4965.2 1623.94
  5046.5 1619.87  5538.9 1622.73  5570.8 1625.62  5646.8 1623.42  5683.2 1640.42
  5993.3 1641.65  6173.3 1634.52  6203.3 1638.79  6283.3  1637.4  6333.3 1644.87
  6943.4    1655  7043.4 1663.18  7443.4 1661.13  7563.5  1671.1  7749.5 1677.19
  7848.2 1683.58  7946.8 1695.92  8373.6 1761.54  8611.1 1771.82  8779.3 1778.54
#Mann= 12 ,-1 , 0
  3769.2     .05       0  3776.4     .08       0  3862.4     .05       0
  3977.7     .08       0  4623.1     .05       0  4965.2    .035       0
  5538.9     .07       0  5570.8     .05       0  7749.5     .05       0
  7848.2     .07       0  7946.8     .12       0  8611.1     .07       0
Bank Sta=4965.2,5538.9
XS Rating Curve= 0 ,0
Exp/Cntr=0.3,0.1

Type RM Length L Ch R = 1 ,2204346 ,121,121,121
BEGIN DESCRIPTION:
Guadalupe River - 160.5
END DESCRIPTION:
XS GIS Cut Line= 6
      1918011.85     13933013.29      1916738.42     13931067.98
       1916095.2     13930503.56      1915661.59     13930151.97
      1915451.53      13929962.3      1914781.38     13928420.61
#Sta/Elev= 30
  1819.2 1676.76  2037.5 1650.64    2476 1642.99  2486.3 1642.57    2819 1641.57
  3249.4 1643.23  3659.7 1645.51  3714.6 1648.22  3849.7 1647.98  4089.8 1649.25
  4166.8 1649.17  4228.7 1648.76  4468.1 1643.99    4654 1621.24  4655.5 1619.24
  4847.7 1621.24  5002.5 1621.96    5198 1622.38  5447.3  1641.5  5723.7 1639.83
  5752.1    1652  5835.9 1653.42  5894.3  1670.9  6066.3 1722.55  6230.9 1793.42
  6497.3  1865.7  6871.1 1921.71  7188.6 1922.97  7408.5 1923.89  7522.3 1913.26
#Mann= 19 ,-1 , 0
  1819.2     .05       0  2037.5     .08       0    2476      .1       0
  2486.3     .08       0    2819      .1       0  3249.4     .08       0
  3659.7      .1       0  3714.6     .08       0  3849.7      .1       0
  4089.8     .08       0  4166.8      .1       0  4228.7     .08       0
    4654     .05       0  4847.7     .08       0  5002.5     .08       0
  5835.9     .05       0  5894.3     .12       0  6497.3     .07       0
  7188.6     .12       0
Bank Sta=4654,4847.7
XS Rating Curve= 0 ,0
Exp/Cntr=0.3,0.1

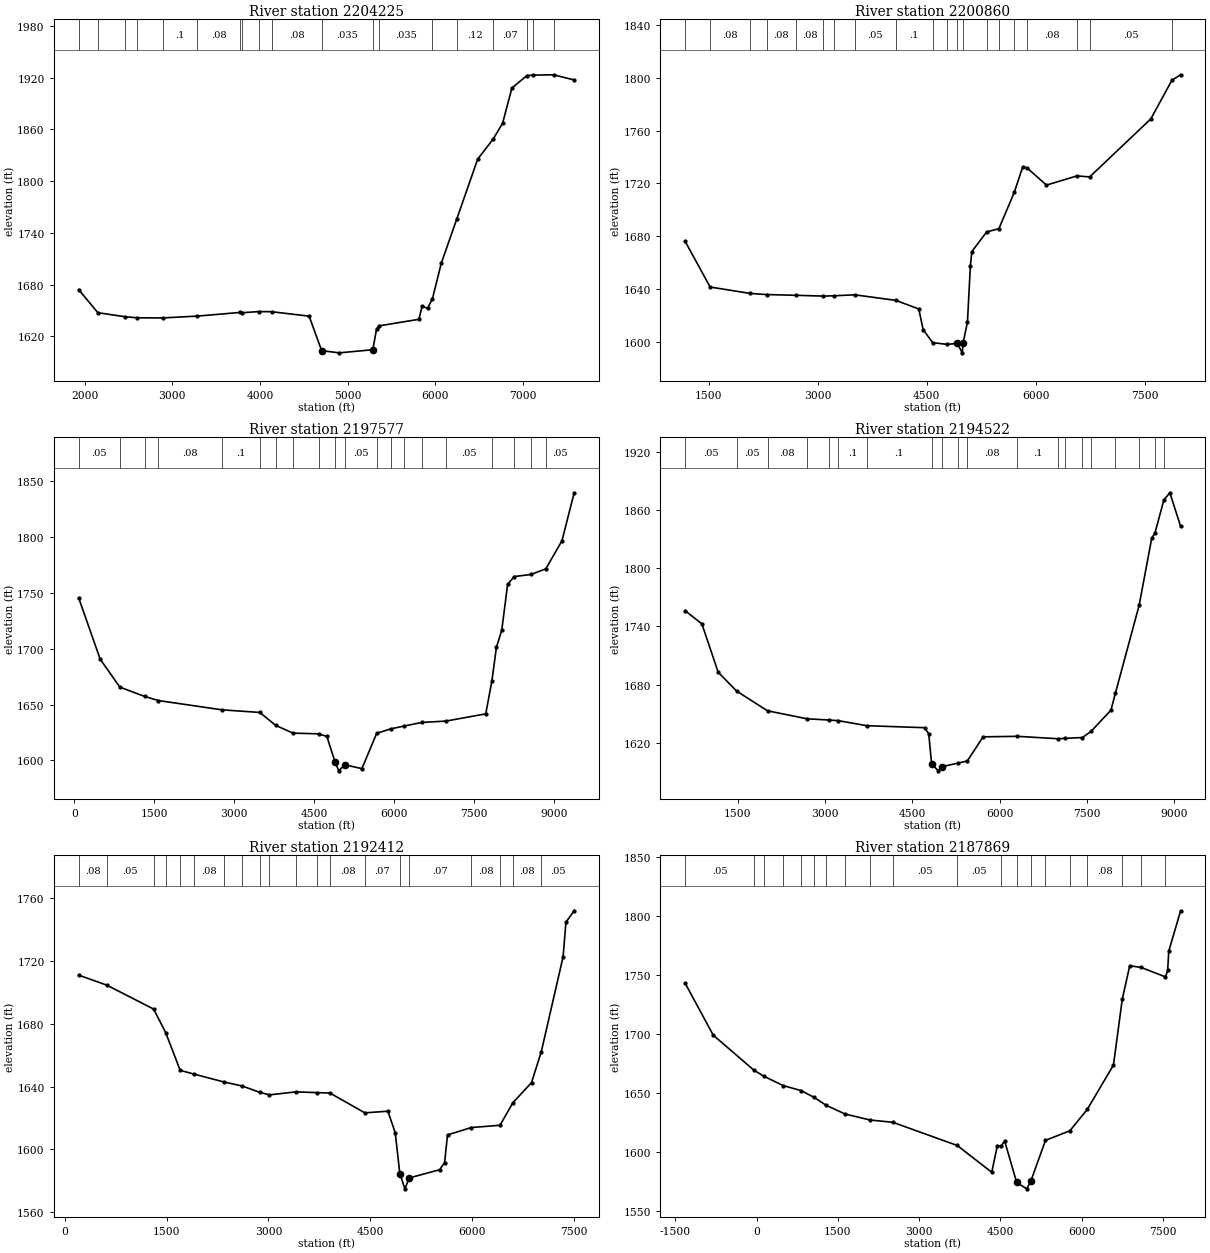
Type RM Length L Ch R = 1 ,2204225 ,3365,3365,3365
BEGIN DESCRIPTION:
Guadalupe River - 160
END DESCRIPTION:
XS GIS Cut Line= 6
      1918051.33     13932944.73      1916763.94     13931015.07
      1915971.37     13930325.37      1915713.59     13930100.94
      1915488.38     13929914.34      1914856.88     13928396.13
#Sta/Elev= 30
  1932.6 1674.21    2152 1647.42  2458.5 1642.81  2599.7 1641.54  2890.8 1641.36
  3285.9 1643.49  3769.1  1647.7  3795.9 1647.41  3984.2 1648.73  4131.5 1648.57
  4559.9 1643.44    4703 1603.48  4903.8 1600.91  5286.1 1604.51  5328.8  1628.5
  5355.9 1632.15  5811.7 1639.78  5847.1  1654.8  5910.9 1652.52  5966.4 1663.81
  6067.5 1705.05  6242.4 1755.76  6481.6 1825.45  6658.7 1848.72  6765.6 1867.06
  6871.8 1907.89    7043 1922.24  7113.7  1922.8  7345.9 1923.19  7581.5 1917.19
#Mann= 19 ,-1 , 0
  1932.6     .05       0    2152     .08       0  2458.5      .1       0
  2599.7     .08       0  2890.8      .1       0  3285.9     .08       0
  3769.1      .1       0  3795.9     .08       0  3984.2      .1       0
  4131.5     .08       0    4703    .035       0  5286.1     .08       0
  5355.9    .035       0  5966.4     .12       0  6242.4     .12       0
  6658.7     .07       0    7043     .12       0  7113.7     .07       0
  7345.9     .12       0
Bank Sta=4703,5286.1
XS Rating Curve= 0 ,0
Exp/Cntr=0.3,0.1

Type RM Length L Ch R = 1 ,2200860 ,3283,3283,3283
BEGIN DESCRIPTION:
Guadalupe River - 159
END DESCRIPTION:
XS GIS Cut Line= 6
      1918398.54     13932771.08      1918509.79      13930028.4
       1918395.1     13929801.59       1918369.6     13929619.86
      1918332.49     13927927.84      1916419.65     13927562.82
#Sta/Elev= 30
  1173.2 1676.23    1518 1641.67  2069.5 1636.82  2294.9 1635.98  2696.1 1635.42
    3073 1634.81  3219.3 1635.04  3509.5 1635.77  4075.3 1631.57  4390.7 1625.06
  4450.7 1609.45  4581.7 1599.59  4778.6 1598.33  4920.8 1598.99  4989.4 1591.91
  5000.8 1599.28  5060.8 1615.37  5100.8 1657.64  5120.9 1668.45  5324.1 1683.26
  5493.2 1685.79  5705.8 1713.28    5821 1732.49  5882.3 1731.69    6148 1718.72
  6569.6 1725.69  6742.9 1724.89  7585.9 1768.83  7876.5 1798.08  7995.6 1802.13
#Mann= 20 ,-1 , 0
  1173.2     .05       0    1518     .08       0  2069.5     .05       0
  2294.9     .08       0  2696.1     .08       0    3073     .05       0
  3219.3     .08       0  3509.5     .05       0  4075.3      .1       0
  4581.7      .1       0  4778.6     .05       0  4920.8     .04       0
  5000.8     .05       0  5324.1     .05       0  5493.2     .08       0
  5705.8     .05       0  5882.3     .08       0  6569.6     .05       0
  6742.9     .05       0  7876.5     .07       0
Bank Sta=4920.8,5000.8
XS Rating Curve= 0 ,0
Exp/Cntr=0.3,0.1

Type RM Length L Ch R = 1 ,2197577 ,3055,3055,3055
BEGIN DESCRIPTION:
Guadalupe River - 158
END DESCRIPTION:
XS GIS Cut Line= 5
      1925542.03     13931286.08      1921333.73      13929348.6
      1920667.07      13926973.6      1920708.73     13925494.43
      1921062.75      13924869.7
#Sta/Elev= 30
    82.2  1745.5   486.3 1690.61   855.6 1665.57  1320.9 1657.23  1577.1 1653.57
  2774.8 1645.24  3481.3 1642.93  3777.2 1631.42  4103.3 1624.44    4584 1623.78
  4739.6 1621.45  4895.4 1598.22  4964.2 1590.69    5072  1596.1    5397 1592.69
  5674.1 1624.21    5935  1628.2  6191.9  1630.8    6527    1634  6971.5 1635.18
  7720.7 1641.65  7835.2 1670.93  7920.8 1701.12  8020.8 1716.34  8130.9 1757.49
  8254.5 1764.48  8572.4 1766.35  8847.7 1771.42  9150.2 1796.41  9379.7 1839.42
#Mann= 20 ,-1 , 0
    82.2     .05       0   855.6     .05       0  1320.9     .08       0
  1577.1     .08       0  2774.8      .1       0  3481.3     .08       0
  3777.2      .1       0  4103.3     .05       0    4584     .05       0
  4895.4     .04       0    5072     .05       0  5674.1     .08       0
    5935      .1       0  6191.9      .1       0    6527     .05       0
  6971.5     .05       0  7835.2     .12       0  8254.5     .05       0
  8572.4     .12       0  8847.7     .05       0
Bank Sta=4895.4,5072
XS Rating Curve= 0 ,0
Exp/Cntr=0.3,0.1

Type RM Length L Ch R = 1 ,2194522 ,2110,2110,2110
BEGIN DESCRIPTION:
Guadalupe River - 157
END DESCRIPTION:
XS GIS Cut Line= 6
      1925724.92     13931416.92      1923874.24     13928071.12
       1923750.8     13928038.67      1922537.61     13926786.83
      1922229.08     13926833.99       1921142.4     13924578.33
#Sta/Elev= 30
   596.4 1756.23   884.3 1742.66  1164.3 1692.87  1481.7 1673.33  2011.8 1653.03
  2691.5 1644.81    3061 1643.55  3223.2 1642.92    3718 1637.69    4710 1635.63
  4780.8 1629.35  4830.2 1598.08  4947.6 1591.16  5007.1 1595.43  5278.2 1599.07
  5442.8 1601.28  5714.3  1626.2  6304.4 1626.74  6999.7 1624.26  7126.6 1624.63
  7421.1 1625.49  7568.9 1631.86  7910.3  1653.7  7987.4 1671.41  8393.9  1761.7
  8611.1 1831.17    8665 1836.17  8819.5 1870.47  8921.9 1877.76  9106.9 1843.09
#Mann= 20 ,-1 , 0
   596.4     .05       0  1481.7     .05       0  2011.8     .08       0
  2691.5      .1       0    3061     .08       0  3223.2      .1       0
    3718      .1       0  4830.2     .04       0  5007.1     .08       0
  5278.2     .05       0  5442.8     .08       0  6304.4      .1       0
  6999.7      .1       0  7126.6     .05       0  7421.1     .08       0
  7568.9     .05       0  7987.4     .12       0  8393.9     .05       0
    8665     .08       0  8819.5     .05       0
Bank Sta=4830.2,5007.1
XS Rating Curve= 0 ,0
Exp/Cntr=0.3,0.1

Type RM Length L Ch R = 1 ,2192412 ,4543,4543,4543
BEGIN DESCRIPTION:
Guadalupe River - 156
END DESCRIPTION:
XS GIS Cut Line= 3
      1926717.93     13930349.76      1925233.54     13926521.59
      1922499.55     13924855.16
#Sta/Elev= 30
   200.8 1710.98   615.2 1704.62  1306.2 1689.37  1484.3 1674.38  1697.9 1650.35
  1897.3 1647.98  2338.8 1642.96  2612.2 1640.34  2872.8 1636.29  3015.1  1634.7
  3406.8  1636.6  3714.2 1636.13  3907.5 1635.84  4421.3 1623.25  4761.7 1624.28
  4869.9  1610.5  4937.4 1584.53  5012.2 1574.83  5075.2 1581.75  5524.5 1587.02
  5598.1  1591.6  5640.7 1609.18  5991.1 1613.87    6415 1615.33    6604 1629.65
    6880 1642.54  7023.8 1662.22  7344.8 1722.59  7387.4 1744.75  7508.5 1751.97
#Mann= 20 ,-1 , 0
   200.8     .08       0   615.2     .05       0  1306.2     .05       0
  1484.3     .08       0  1697.9     .05       0  1897.3     .08       0
  2338.8     .05       0  2612.2     .08       0  2872.8     .05       0
  3015.1     .08       0  3406.8     .08       0  3714.2      .1       0
  3907.5     .08       0  4421.3     .07       0  4937.4     .04       0
  5075.2     .07       0  5991.1     .08       0    6415     .08       0
    6604     .08       0  7023.8     .05       0
Bank Sta=4937.4,5075.2
XS Rating Curve= 0 ,0
Exp/Cntr=0.3,0.1

Type RM Length L Ch R = 1 ,2187869 ,2232,2232,2232
BEGIN DESCRIPTION:
Guadalupe River - 155
END DESCRIPTION:
XS GIS Cut Line= 6
      1930794.33     13925097.47      1925442.77     13922231.97
      1924821.35     13921912.02      1924529.14     13921756.95
      1924184.02     13921667.72      1922495.71     13921694.71
#Sta/Elev= 30
 -1319.9 1743.07    -800 1698.92   -49.6 1669.24   133.5 1664.15   487.6 1656.23
   819.9 1651.97  1060.8 1646.24    1279 1639.63  1628.3 1632.15  2092.7 1627.04
  2513.7 1625.08  3702.2 1605.44    4339 1582.73  4443.1 1605.33  4508.2 1604.69
  4577.3 1609.26  4798.6 1574.16  4984.9 1568.68  5060.1  1575.2  5331.2 1609.74
  5781.8 1617.95    6102    1636  6585.9 1673.66  6748.2 1729.51  6885.9  1757.8
    7095 1756.37    7545 1748.35    7586 1753.77    7606 1770.19  7825.3 1804.38
#Mann= 20 ,-1 , 0
 -1319.9     .05       0   -49.6     .08       0   133.5     .05       0
   487.6     .07       0   819.9     .05       0  1060.8     .05       0
    1279     .08       0  1628.3     .06       0  2092.7     .08       0
  2513.7     .05       0  3702.2     .05       0  4508.2     .05       0
  4798.6     .04       0  5060.1     .08       0  5331.2      .1       0
  5781.8     .08       0    6102     .08       0  6748.2     .05       0
    7095     .07       0    7545     .05       0
Bank Sta=4798.6,5060.1
XS Rating Curve= 0 ,0
Exp/Cntr=0.3,0.1