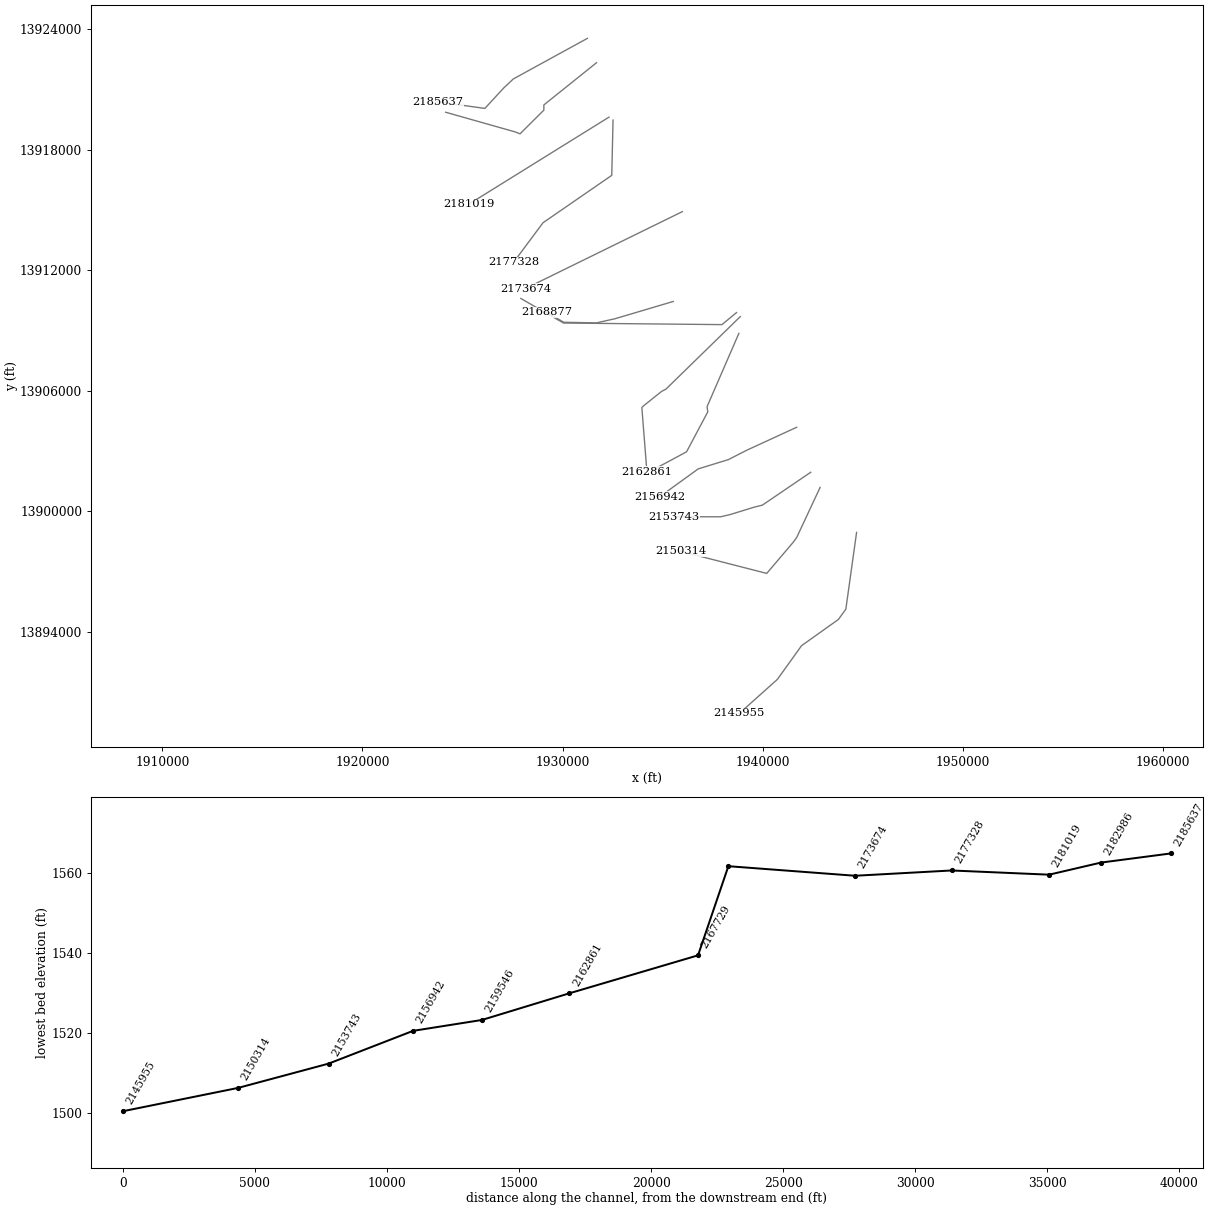
HEC-RAS study Guadalupe River.prj: Guadalupe River Base Level Engineering

--- Guadalupe River.g01 (geometry) --- (continued)

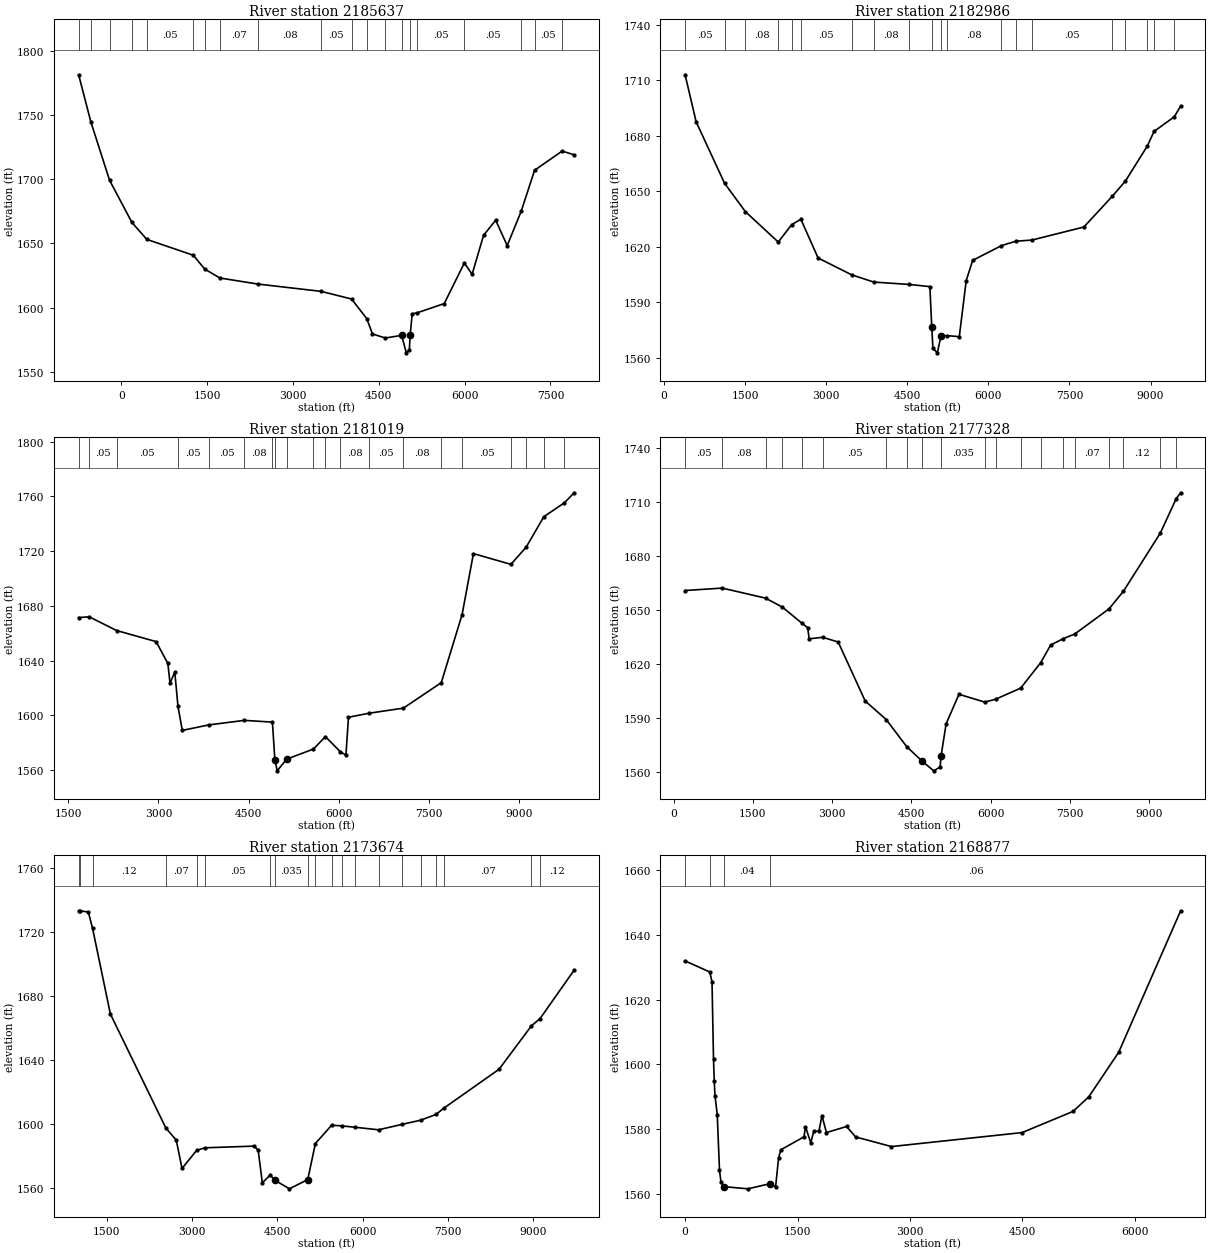
Type RM Length L Ch R = 1 ,2185637 ,2651,2651,2651
BEGIN DESCRIPTION:
Guadalupe River - 154
END DESCRIPTION:
XS GIS Cut Line= 6
      1931245.78       13923535.      1927541.78     13921513.32
      1927066.62     13921068.18      1926672.42       13920644.
      1926119.84     13920045.99      1923745.77     13920375.27
#Sta/Elev= 30
  -745.4  1781.3  -532.7 1744.79  -205.2 1699.23     185 1666.41   445.2 1653.18
    1259 1640.79  1458.1 1630.06  1723.5  1623.1  2384.1  1618.4  3493.5 1612.69
  4024.7 1606.74  4290.1 1591.51  4390.5 1579.52  4614.9  1576.4  4900.2 1578.42
  4981.4 1564.84  5034.6 1567.07  5048.7 1578.34  5084.3 1595.26  5166.8 1595.93
  5644.8  1603.2  5995.4 1634.76  6132.4 1626.01  6331.4  1656.3  6543.4  1668.1
  6745.3 1648.32  6990.4 1675.16  7223.7 1706.98  7704.7 1721.87  7915.6 1719.01
#Mann= 20 ,-1 , 0
  -745.4     .07       0  -532.7     .12       0  -205.2     .05       0
     185     .08       0   445.2     .05       0    1259     .12       0
  1458.1     .05       0  1723.5     .07       0  2384.1     .08       0
  3493.5     .05       0  4024.7     .08       0  4290.1     .07       0
  4614.9     .05       0  4900.2     .04       0  5048.7     .12       0
  5166.8     .05       0  5995.4     .05       0  6990.4     .08       0
  7223.7     .05       0  7704.7     .08       0
Bank Sta=4900.2,5048.7
XS Rating Curve= 0 ,0
Exp/Cntr=0.3,0.1

Type RM Length L Ch R = 1 ,2182986 ,1967,1967,1967
BEGIN DESCRIPTION:
Guadalupe River - 153
END DESCRIPTION:
XS GIS Cut Line= 6
      1931697.18     13922319.74      1929067.15     13920218.59
      1929067.14     13919959.15      1927877.98     13918782.15
      1927634.01     13918875.77      1924162.46     13919854.42
#Sta/Elev= 30
   389.9 1712.98   594.4 1687.53  1121.3 1654.21  1507.1 1638.89  2113.7 1622.48
  2363.5 1631.97  2532.1 1634.79  2850.2 1613.86  3469.6 1604.79  3879.5 1600.84
  4527.9 1599.57  4918.1 1598.37  4953.4 1576.35  4974.7 1564.97  5056.7 1562.55
  5123.2  1571.7  5227.1 1571.87  5462.6  1571.3  5589.8 1601.55  5709.8 1612.58
  6242.8 1620.55  6504.8 1622.92    6808 1623.58  7767.3 1630.62  8289.4 1647.14
  8536.1  1655.5  8939.3 1674.34  9065.4 1682.34  9438.5 1690.22  9557.4 1696.01
#Mann= 20 ,-1 , 0
   389.9     .05       0  1121.3     .08       0  1507.1     .08       0
  2113.7     .05       0  2363.5     .08       0  2532.1     .05       0
  3469.6     .05       0  3879.5     .08       0  4527.9     .08       0
  4953.4     .04       0  5123.2     .07       0  5227.1     .08       0
  6242.8     .05       0  6504.8     .08       0    6808     .05       0
  8289.4     .08       0  8536.1     .05       0  8939.3     .08       0
  9065.4     .05       0  9438.5     .08       0
Bank Sta=4953.4,5123.2
XS Rating Curve= 0 ,0
Exp/Cntr=0.3,0.1

Type RM Length L Ch R = 1 ,2181019 ,3691,3691,3691
BEGIN DESCRIPTION:
Guadalupe River - 152
END DESCRIPTION:
XS GIS Cut Line= 2
      1932322.15     13919611.38       1925309.1     13915271.62
#Sta/Elev= 30
  1671.6 1671.47  1847.1 1672.06  2304.1 1662.02  2961.2 1653.92  3156.2 1638.01
  3192.8  1623.6    3272 1631.65    3325 1606.55  3396.9 1589.05  3833.3 1593.05
  4429.1 1596.39    4897 1595.12  4937.2 1567.65  4976.2 1559.52  5132.2 1568.01
  5579.6 1575.44  5779.3 1584.51  6029.1 1573.38  6120.2 1571.03  6162.7 1598.67
  6508.1 1601.63  7076.5 1605.33  7707.1 1623.92  8053.8  1673.7    8242 1718.22
  8865.6 1710.36  9120.4 1722.96  9413.2 1745.14  9755.6 1755.33  9918.8 1762.65
#Mann= 20 ,-1 , 0
  1671.6     .08       0  1847.1     .05       0  2304.1     .05       0
    3325     .05       0  3833.3     .05       0  4429.1     .08       0
    4897     .07       0  4937.2     .04       0  5132.2     .07       0
  5579.6     .07       0  5779.3     .05       0  6029.1     .08       0
  6508.1     .05       0  7076.5     .08       0  7707.1     .05       0
  8053.8     .05       0  8865.6     .08       0  9120.4     .05       0
  9413.2     .08       0  9755.6     .05       0
Bank Sta=4937.2,5132.2
XS Rating Curve= 0 ,0
Exp/Cntr=0.3,0.1

Type RM Length L Ch R = 1 ,2177328 ,3654,3654,3654
BEGIN DESCRIPTION:
Guadalupe River - 151
END DESCRIPTION:
XS GIS Cut Line= 4
       1932525.2     13919464.28      1932461.66     13916713.26
      1929024.16     13914352.84      1927551.25     13912380.97
#Sta/Elev= 30
   216.4 1660.67   919.1 1662.01  1739.4 1656.44  2058.5 1651.46  2428.6 1642.52
  2536.3 1640.08  2566.3 1633.85  2822.4  1634.7  3115.5 1632.06  3626.4 1599.33
  4023.9 1589.06  4410.6 1574.06    4705 1565.93  4923.8 1560.57  5044.3 1562.67
  5063.6 1568.95  5159.1 1586.71  5402.4 1603.05  5890.4 1598.72  6094.7 1600.31
  6570.8 1606.49  6949.2  1620.6  7138.1  1630.4  7370.8 1633.87  7594.7 1636.52
  8244.8 1650.52  8517.1  1660.3  9213.8 1692.51  9516.3 1711.74  9599.3 1714.92
#Mann= 20 ,-1 , 0
   216.4     .05       0   919.1     .08       0  1739.4     .05       0
  2058.5     .08       0  2428.6     .08       0  2822.4     .05       0
  4023.9     .05       0  4410.6     .07       0    4705     .04       0
  5063.6    .035       0  5890.4     .05       0  6094.7     .07       0
  6570.8     .05       0  6949.2     .12       0  7370.8     .05       0
  7594.7     .07       0  8244.8     .05       0  8517.1     .12       0
  9213.8     .05       0  9516.3     .12       0
Bank Sta=4705,5063.6
XS Rating Curve= 0 ,0
Exp/Cntr=0.3,0.1

Type RM Length L Ch R = 1 ,2173674 ,4797,4797,4797
BEGIN DESCRIPTION:
Guadalupe River - 150
END DESCRIPTION:
XS GIS Cut Line= 2
      1935988.71     13914906.99      1928151.32     13911079.43
#Sta/Elev= 30
  1003.3 1733.23  1026.8 1733.16  1173.8  1732.5  1247.4 1722.41  1562.2 1668.63
  2539.2 1597.27  2721.3 1589.78  2823.2 1572.01  3079.3 1583.28  3226.6 1584.93
  4090.1 1585.98  4163.2 1583.54  4236.3 1563.04  4374.7 1567.86  4461.5 1564.56
  4714.1 1559.25  5036.1 1565.07  5170.1 1587.59  5455.7 1599.03  5633.9 1598.66
  5871.9 1597.77  6281.4 1596.19  6699.5 1599.61  7023.6  1602.2  7295.3 1605.82
  7427.5 1609.64  8402.5 1634.04  8972.5 1661.21  9125.4 1665.81  9725.4  1696.1
#Mann= 20 ,-1 , 0
  1003.3      .1       0  1026.8     .05       0  1247.4     .12       0
  2539.2     .07       0  3079.3     .08       0  3226.6     .05       0
  4374.7    .035       0  4461.5    .035       0  5036.1    .035       0
  5170.1     .08       0  5455.7     .05       0  5633.9     .07       0
  5871.9     .05       0  6281.4     .05       0  6699.5     .07       0
  7023.6     .05       0  7295.3     .05       0  7427.5     .07       0
  8972.5     .05       0  9125.4     .12       0
Bank Sta=4461.5,5036.1
XS Rating Curve= 0 ,0
Exp/Cntr=0.3,0.1

Type RM Length L Ch R = 1 ,2168877 ,1148,1148,1148
XS GIS Cut Line= 5
  1935534.97196213910435.1097455 1932626.985652913909575.7348238
 1931696.420256813909368.9425865 1930058.450107613909399.1908856
 1929209.122409913909899.6872599
#Sta/Elev= 30
       0 1631.94  329.17 1628.53  359.09 1625.49  379.04 1601.54  389.01 1594.83
  398.99  1590.3  428.91 1584.56  458.84 1567.35  478.79 1563.67  518.68 1562.32
  837.88 1561.64 1137.12 1563.26 1206.94 1562.22 1246.84 1571.19 1276.76 1573.68
 1585.98 1577.69 1605.93 1580.82 1675.75 1575.86 1715.65 1579.35 1785.47 1579.45
 1825.37 1584.23 1885.22    1579 2154.54 1580.87 2274.23 1577.65 2753.02 1574.68
 4495.03 1578.99 5174.31 1585.52 5384.09 1590.01 5783.17 1603.75 6609.68 1647.41
#Mann= 4 ,-1 , 0
       0      .1       0  329.17     .12       0  518.68     .04       0
 1137.12     .06       0
Bank Sta=518.68,1137.12
XS Rating Curve= 0 ,0
Exp/Cntr=0.3,0.1

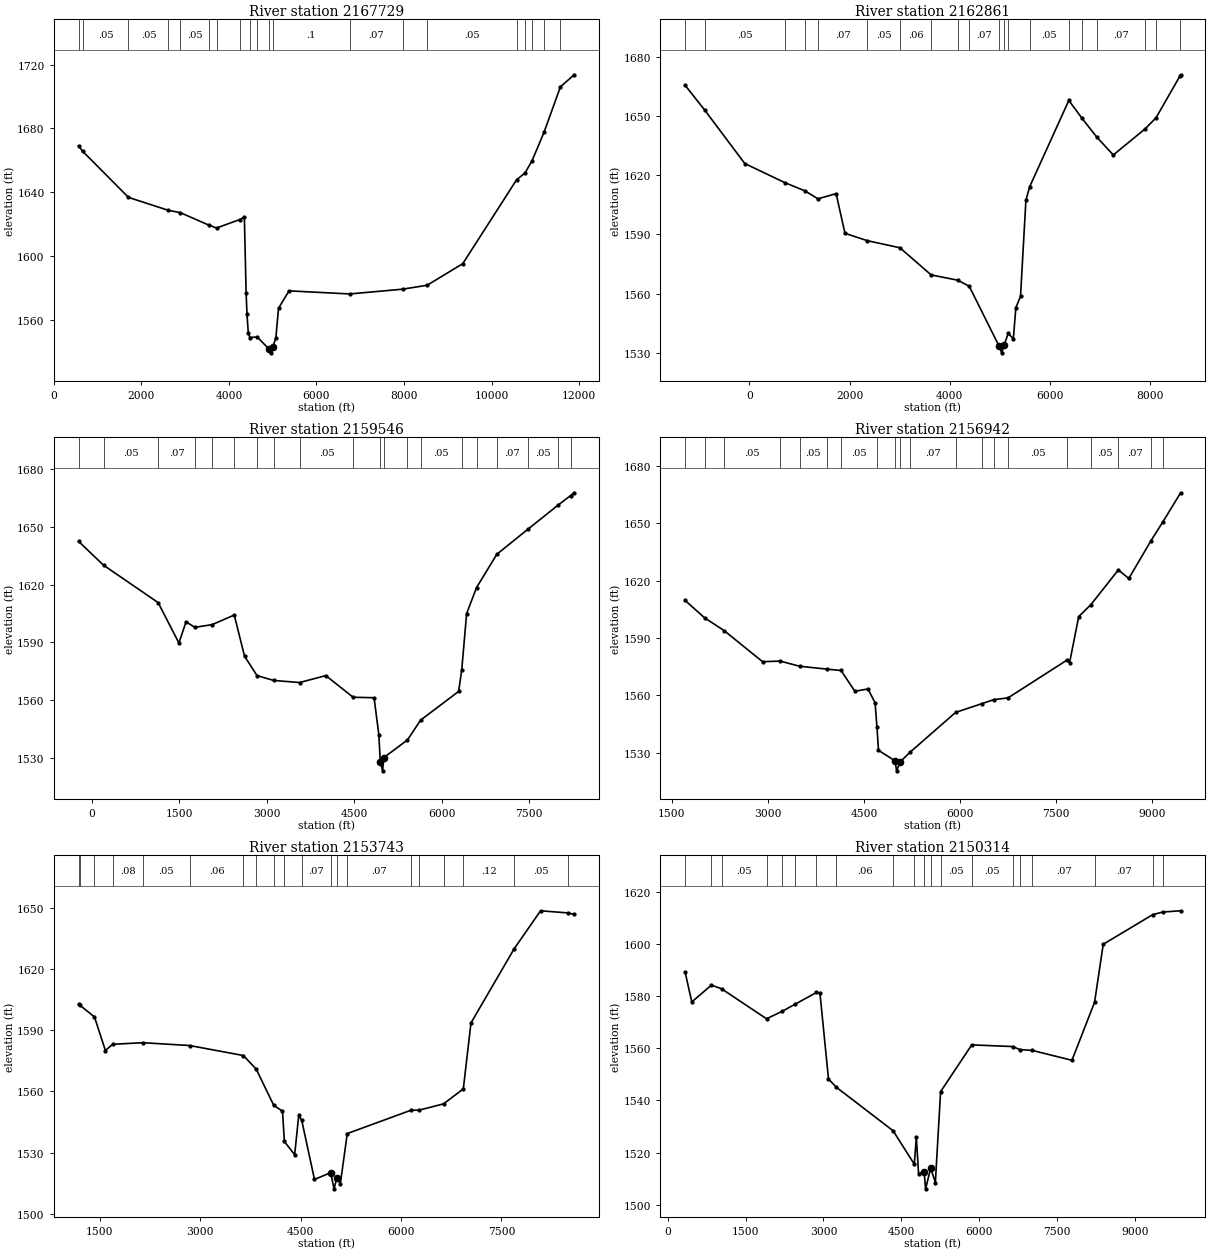
Type RM Length L Ch R = 1 ,2167729 ,4868,4868,4868
BEGIN DESCRIPTION:
Guadalupe River - 149
END DESCRIPTION:
XS GIS Cut Line= 4
      1938697.05     13909880.94      1937967.91     13909282.01
      1930051.24     13909360.13       1927915.8     13910584.11
#Sta/Elev= 30
   565.9 1669.03   657.1 1665.67  1704.8 1636.76  2615.4 1628.65  2888.8 1627.21
  3543.4 1619.35    3716 1617.56  4243.3 1622.84  4352.5 1624.36  4392.5 1577.07
  4412.5 1563.57  4442.5 1551.71  4478.8 1548.95  4644.6 1549.28  4926.6 1541.44
  4964.1 1539.34  5002.6 1543.09  5072.6  1548.8  5132.6 1567.24  5372.6 1578.18
  6759.5 1576.25  7966.3 1579.23  8527.1 1581.68  9342.8 1595.23 10571.6 1647.77
 10765.7 1652.08 10926.5 1659.79 11199.3 1677.55 11574.2 1706.09 11887.9  1713.6
#Mann= 20 ,-1 , 0
   565.9     .05       0   657.1     .05       0  1704.8     .05       0
  2615.4     .08       0  2888.8     .05       0  3543.4     .08       0
    3716     .05       0  4243.3     .12       0  4478.8     .07       0
  4644.6     .12       0  4926.6     .04       0  5002.6      .1       0
  6759.5     .07       0  7966.3     .06       0  8527.1     .05       0
 10571.6     .07       0 10765.7     .07       0 10926.5     .05       0
 11199.3     .05       0 11574.2     .05       0
Bank Sta=4926.6,5002.6
XS Rating Curve= 0 ,0
Exp/Cntr=0.3,0.1

Type RM Length L Ch R = 1 ,2162861 ,3315,3315,3315
BEGIN DESCRIPTION:
Guadalupe River - 148
END DESCRIPTION:
XS GIS Cut Line= 6
      1938884.62      13909680.8      1935172.05     13906072.25
      1934947.02     13905953.34       1934053.7      13905241.5
       1933965.2     13905152.58      1934217.91     13901964.33
#Sta/Elev= 30
 -1286.1 1665.83  -891.2 1653.08   -94.2 1626.05   701.6 1616.38  1110.4 1612.12
  1368.3 1608.11  1730.3 1610.75    1907 1590.58  2354.1 1586.84  3003.5 1583.25
  3628.2 1569.45  4160.2 1566.76  4389.3 1563.68  4979.3 1533.57  5038.4 1529.85
    5085 1533.69  5167.6 1539.69  5270.8 1537.03    5320 1552.83  5413.5 1558.53
  5521.4 1607.51    5597 1614.29  6378.5  1658.1  6644.1 1648.94  6939.4 1639.38
  7266.8 1630.39  7905.2 1643.73  8120.5  1649.3  8597.1 1670.46  8611.7 1671.14
#Mann= 20 ,-1 , 0
 -1286.1     .05       0  -891.2     .05       0   701.6     .07       0
  1110.4     .05       0  1368.3     .07       0  2354.1     .05       0
  3003.5     .06       0  3628.2     .06       0  4160.2     .05       0
  4389.3     .07       0  4979.3     .04       0    5085     .07       0
  5167.6     .07       0    5597     .05       0  6378.5     .07       0
  6644.1     .05       0  6939.4     .07       0  7905.2     .05       0
  8120.5     .07       0  8597.1     .05       0
Bank Sta=4979.3,5085
XS Rating Curve= 0 ,0
Exp/Cntr=0.3,0.1

Type RM Length L Ch R = 1 ,2159546 ,2604,2604,2604
BEGIN DESCRIPTION:
Guadalupe River - 147
END DESCRIPTION:
XS GIS Cut Line= 6
      1938815.22     13908847.52      1937227.05     13905203.51
      1937258.66     13904934.74      1936205.37     13902959.52
      1936185.23      13902941.2       1934440.2     13902007.21
#Sta/Elev= 30
    -221 1642.55     206 1630.17  1141.4 1610.71  1496.9 1589.67  1619.5 1600.72
  1770.1 1597.84    2067 1599.25  2445.1 1604.25  2621.9 1582.82  2835.6 1572.74
  3121.1  1570.2  3565.5 1569.12  4014.3 1572.73  4482.5 1561.46  4841.2 1561.21
  4922.6 1541.99  4948.6 1527.61  4988.1 1523.17  5004.5 1529.96  5412.6 1539.24
  5639.5 1549.58  6290.4 1564.51  6343.3  1575.7  6426.8 1604.98  6596.8 1618.52
    6944 1635.85  7475.2 1648.85    7996 1661.49  8207.4 1666.38  8269.7 1667.86
#Mann= 20 ,-1 , 0
    -221     .05       0     206     .05       0  1141.4     .07       0
  1770.1     .07       0    2067     .07       0  2445.1     .07       0
  2835.6     .05       0  3121.1     .06       0  3565.5     .05       0
  4482.5     .05       0  4948.6     .04       0  5004.5     .12       0
  5412.6     .05       0  5639.5     .05       0  6343.3     .07       0
  6596.8     .07       0    6944     .07       0  7475.2     .05       0
    7996     .05       0  8207.4     .07       0
Bank Sta=4948.6,5004.5
XS Rating Curve= 0 ,0
Exp/Cntr=0.3,0.1

Type RM Length L Ch R = 1 ,2156942 ,3199,3199,3199
BEGIN DESCRIPTION:
Guadalupe River - 146
END DESCRIPTION:
XS GIS Cut Line= 6
      1941702.74     13904171.08      1939195.17     13903022.14
      1938955.98      13902900.4      1938289.81     13902561.27
       1936780.6     13902098.58      1934853.77     13900707.54
#Sta/Elev= 30
  1710.4 1609.68  2014.9 1600.56  2321.5 1593.83  2918.4 1577.61  3194.1 1577.92
    3497 1575.21  3924.5 1573.71  4142.4    1573  4359.1 1562.11  4562.9 1563.33
  4674.1 1556.06  4702.3 1543.64  4726.9 1531.21  4985.5 1525.67  5009.2 1520.45
  5068.9 1525.31  5218.3 1530.17  5929.7 1551.05  6339.3 1555.63  6523.2 1557.71
  6748.7 1558.68  7670.8 1578.53  7707.5 1577.12  7849.9 1601.23  8038.3 1607.42
  8467.8 1625.66  8631.3 1621.19    8978 1641.02  9158.6 1650.62  9439.6 1666.06
#Mann= 20 ,-1 , 0
  1710.4     .05       0  2014.9     .08       0  2321.5     .05       0
  3194.1     .08       0    3497     .05       0  3924.5     .08       0
  4142.4     .05       0  4702.3     .12       0  4985.5     .04       0
  5068.9     .07       0  5218.3     .07       0  5929.7     .05       0
  6339.3     .05       0  6523.2     .12       0  6748.7     .05       0
  7670.8     .12       0  8038.3     .05       0  8467.8     .07       0
    8978     .07       0  9158.6     .05       0
Bank Sta=4985.5,5068.9
XS Rating Curve= 0 ,0
Exp/Cntr=0.3,0.1

Type RM Length L Ch R = 1 ,2153743 ,3429,3429,3429
BEGIN DESCRIPTION:
Guadalupe River - 145
END DESCRIPTION:
XS GIS Cut Line= 6
      1942405.83     13901931.48      1939986.71     13900294.09
      1939572.93     13900191.76      1938380.96     13899826.42
      1937901.97     13899714.24      1935582.94     13899717.94
#Sta/Elev= 30
  1182.4 1602.78  1197.4 1602.42  1419.1 1596.55  1582.7 1580.09  1690.9 1583.14
  2143.5 1583.92  2842.6 1582.53  3644.2 1577.63  3836.1 1570.94  4097.9 1553.23
  4228.9 1550.35    4257 1535.48  4410.7 1528.97  4471.6 1548.32  4516.4 1545.84
  4706.6 1516.87  4948.2 1520.17  4999.3 1512.25  5042.1 1517.77  5093.2 1514.67
  5196.6 1539.36  6149.6 1550.81  6267.5 1550.82  6635.2 1553.91  6930.9 1561.26
  7045.5 1593.61  7691.1 1630.01  8085.5 1648.62  8493.3 1647.57  8587.6 1646.87
#Mann= 20 ,-1 , 0
  1182.4     .07       0  1197.4     .08       0  1419.1     .05       0
  1690.9     .08       0  2143.5     .05       0  2842.6     .06       0
  3644.2     .07       0  3836.1     .05       0  4097.9     .07       0
    4257     .05       0  4516.4     .07       0  4948.2     .04       0
  5042.1     .07       0  5196.6     .07       0  6149.6     .05       0
  6267.5     .07       0  6635.2     .05       0  6930.9     .12       0
  7691.1     .05       0  8493.3     .12       0
Bank Sta=4948.2,5042.1
XS Rating Curve= 0 ,0
Exp/Cntr=0.3,0.1

Type RM Length L Ch R = 1 ,2150314 ,4359,4359,4359
BEGIN DESCRIPTION:
Guadalupe River - 144
END DESCRIPTION:
XS GIS Cut Line= 6
      1942874.59     13901176.29      1941702.67     13898681.12
      1941530.16     13898445.45       1940216.6     13896906.27
      1940206.04     13896895.67      1935895.44     13897999.18
#Sta/Elev= 30
   337.1 1589.21   465.5 1577.73   843.6 1584.18    1038 1582.79  1904.6 1571.29
  2205.7 1574.15  2453.1 1576.86  2864.9 1581.37  2932.3 1581.14  3096.7 1548.23
  3246.1  1545.1  4340.5 1528.41  4748.9 1515.59  4787.2 1526.12    4830 1511.99
  4936.6 1512.71  4965.7 1506.17  5063.9 1514.11  5153.5 1508.58  5254.3  1543.4
  5853.7  1561.3  6641.3 1560.66  6776.9 1559.51  7020.4 1559.17  7782.2 1555.39
  8217.5 1577.61    8384 1599.83  9337.5 1611.18  9528.7 1612.17  9873.9 1612.65
#Mann= 20 ,-1 , 0
   337.1     .05       0   843.6     .08       0    1038     .05       0
  1904.6     .07       0  2205.7     .07       0  2453.1     .05       0
  2864.9     .07       0  3246.1     .06       0  4340.5     .05       0
  4748.9     .07       0  4936.6     .04       0  5063.9     .07       0
  5254.3     .05       0  5853.7     .05       0  6641.3     .06       0
  6776.9     .05       0  7020.4     .07       0  8217.5     .07       0
  9337.5     .05       0  9528.7     .12       0
Bank Sta=4936.6,5063.9
XS Rating Curve= 0 ,0
Exp/Cntr=0.3,0.1

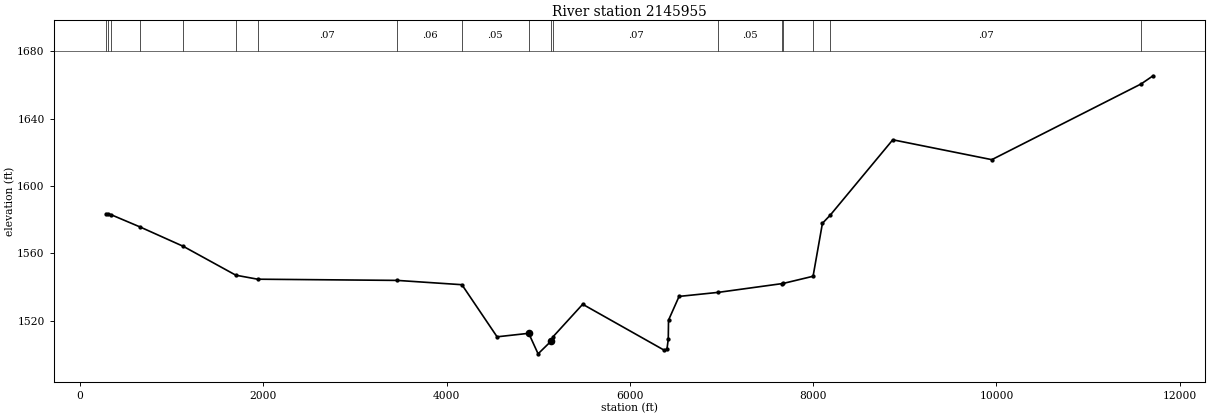
Type RM Length L Ch R = 1 ,2145955 ,3304,3304,3304
BEGIN DESCRIPTION:
Guadalupe River - 143
END DESCRIPTION:
XS GIS Cut Line= 6
      1944697.49     13898936.67      1944160.69     13895114.74
      1943788.18     13894601.86      1941947.13     13893296.94
      1940739.16     13891618.98      1938839.07     13889927.12
#Sta/Elev= 30
     287  1583.5   312.1 1583.27   336.3 1583.05     656 1575.69  1128.6 1564.16
  1701.7 1547.03  1939.5 1544.66  3461.3 1543.95  4168.1 1541.39  4551.9 1510.45
  4897.1 1512.53  4999.3 1500.34  5140.8 1507.87  5162.6  1510.5  5485.9 1529.78
  6377.2 1502.44  6405.5 1503.14  6419.7 1509.12  6422.3 1520.33  6537.5 1534.44
  6967.6 1536.86  7661.1 1542.04  7671.7 1542.12  7999.6 1546.41  8101.6 1577.85
  8186.9  1582.7  8869.2 1627.44  9949.7 1615.64 11579.3 1660.62 11709.2 1665.45
#Mann= 18 ,-1 , 0
     287     .07       0   312.1     .05       0   336.3     .07       0
     656     .05       0  1128.6     .07       0  1701.7     .12       0
  1939.5     .07       0  3461.3     .06       0  4168.1     .05       0
  4897.1     .04       0  5140.8     .07       0  5162.6     .07       0
  6967.6     .05       0  7661.1     .12       0  7671.7     .07       0
  7999.6     .12       0  8186.9     .07       0 11579.3     .12       0
Bank Sta=4897.1,5140.8
XS Rating Curve= 0 ,0
Exp/Cntr=0.3,0.1