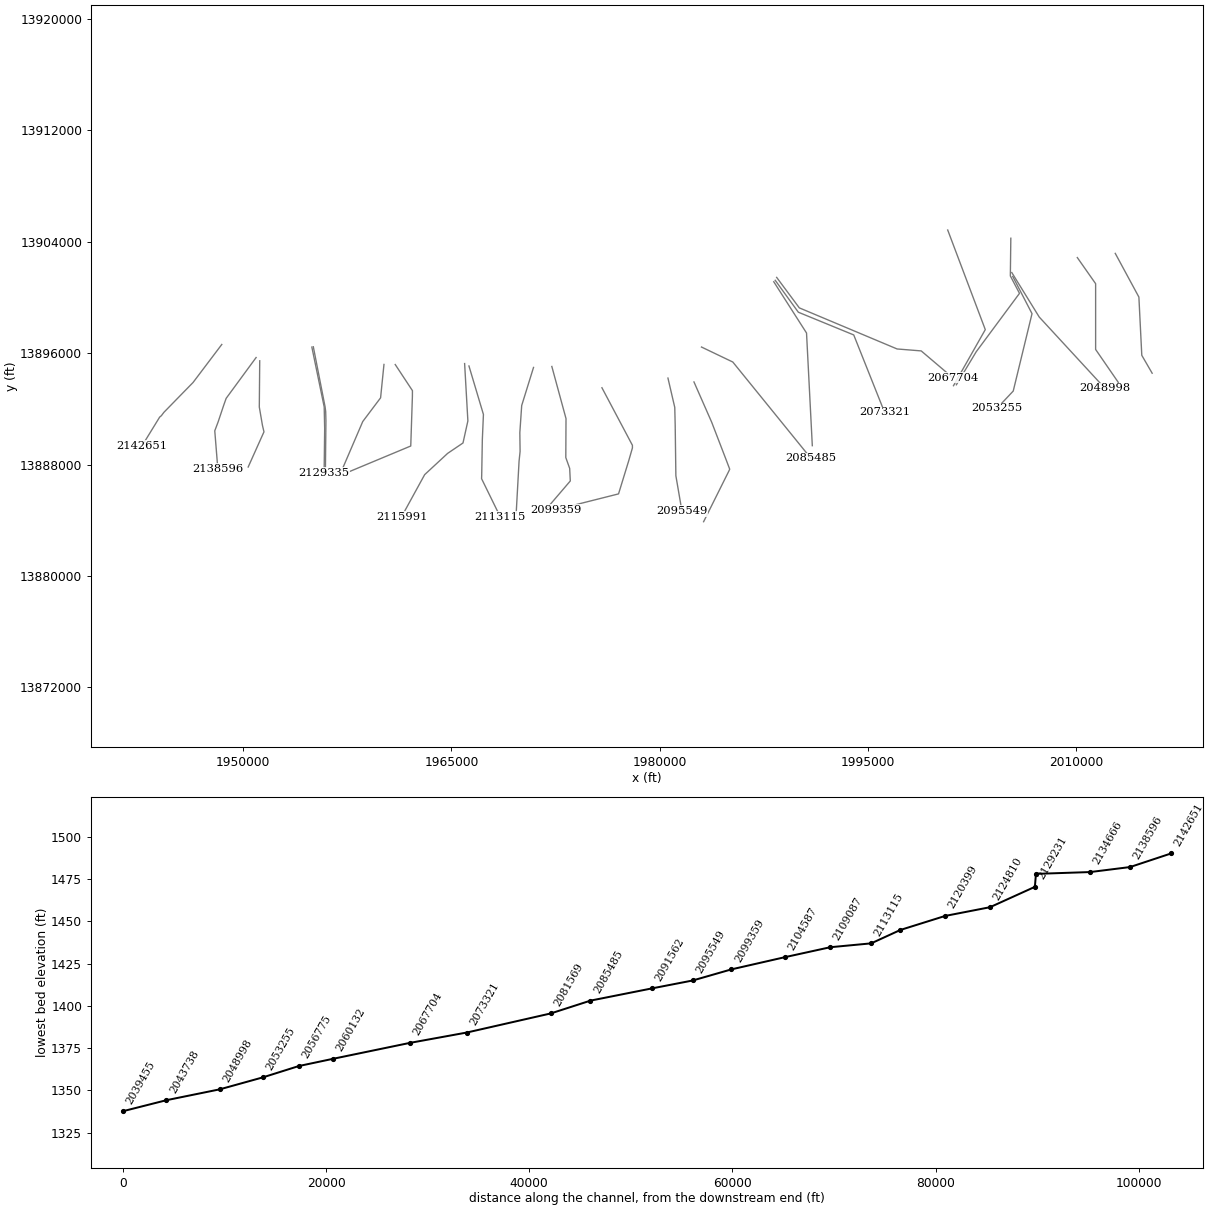
HEC-RAS study Guadalupe River.prj: Guadalupe River Base Level Engineering

--- Guadalupe River.g01 (geometry) --- (continued)

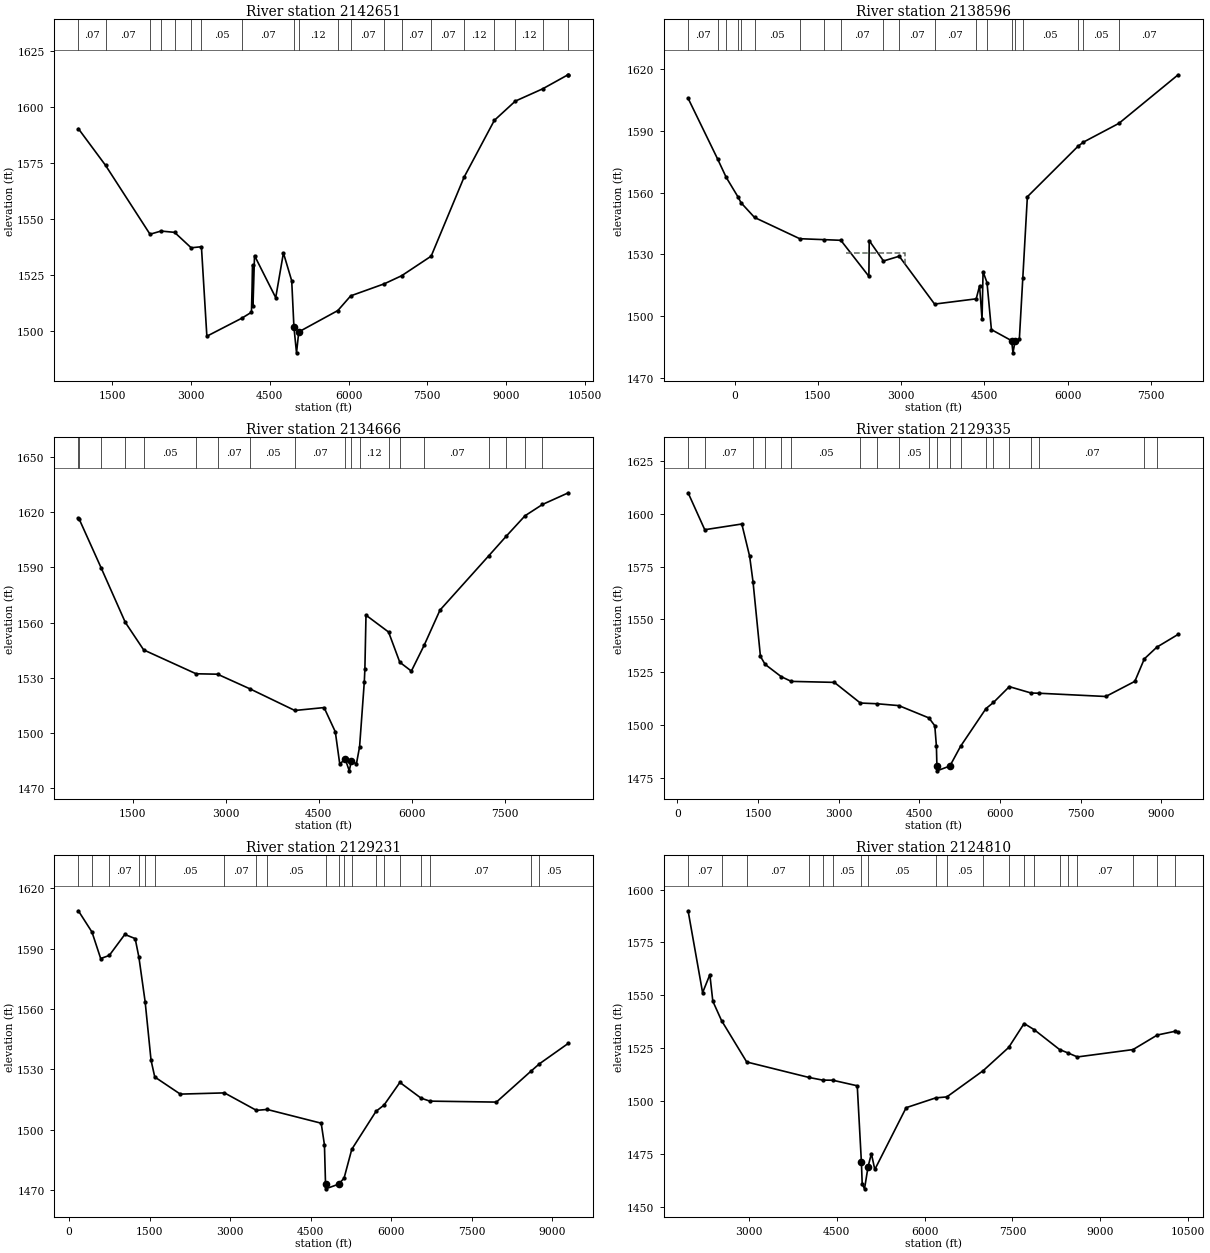
Type RM Length L Ch R = 1 ,2142651 ,4055,4055,4055
BEGIN DESCRIPTION:
Guadalupe River - 142
END DESCRIPTION:
XS GIS Cut Line= 6
      1948447.48     13896618.96      1946377.63     13893889.41
      1944281.43     13891752.09      1944091.81     13891502.92
      1943970.22     13891402.85      1942693.09     13889328.62
#Sta/Elev= 30
   858.1 1590.25  1374.9 1573.91  2221.9 1543.17  2430.7 1544.59  2689.4 1544.01
  3004.8 1537.13  3200.3  1537.6  3303.7  1497.7  3971.2 1505.77  4152.4 1508.39
  4175.2 1529.46  4181.5 1511.16  4210.6 1533.65  4614.2  1514.9  4760.6 1534.84
  4918.6  1522.4  4960.8 1501.73    5010 1490.29  5052.7 1499.63  5796.4 1509.15
  6041.5  1515.7  6680.5 1521.07  7009.7 1524.66  7572.5  1533.4  8198.5  1568.6
  8774.8 1593.95  9174.1 1602.53  9692.5 1607.98 10176.1 1614.27 10184.1 1614.26
#Mann= 20 ,-1 , 0
   858.1     .07       0  1374.9     .07       0  2221.9     .08       0
  2430.7     .07       0  2689.4     .05       0  3004.8     .07       0
  3200.3     .05       0  3971.2     .07       0  4960.8     .04       0
  5052.7     .12       0  5796.4     .07       0  6041.5     .07       0
  6680.5     .12       0  7009.7     .07       0  7572.5     .07       0
  8198.5     .12       0  8774.8     .07       0  9174.1     .12       0
  9692.5     .12       0 10176.1     .12       0
#XS Ineff= 2 , 0
       0 4764.84 1534.46               0
Permanent Ineff=
       F       F
Bank Sta=4960.8,5052.7
XS Rating Curve= 0 ,0
Exp/Cntr=0.3,0.1

Type RM Length L Ch R = 1 ,2138596 ,3930,3930,3930
BEGIN DESCRIPTION:
Guadalupe River - 141
END DESCRIPTION:
XS GIS Cut Line= 6
      1950921.46     13895681.48      1948762.36     13892749.62
      1948580.86     13892239.77      1948186.21     13891064.34
      1947942.16     13890419.49      1948161.04     13887712.71
#Sta/Elev= 30
  -838.2 1605.74  -304.4 1576.17  -152.4 1567.41    64.3 1557.72   115.6 1555.04
   358.8 1547.91  1172.8  1537.6  1602.3 1537.15  1913.4 1536.82  2418.5 1519.34
  2424.7 1536.68  2681.4 1526.79  2965.2 1529.09  3602.2 1505.87  4351.8 1508.42
  4412.3  1514.7  4456.9 1498.51  4475.4 1521.61  4546.6 1516.25  4625.5 1493.48
  4989.8  1488.1  5014.5 1482.21  5051.2 1487.84  5128.8 1488.76  5191.4 1518.59
  5273.4 1557.96    6182 1582.35  6280.5 1584.43  6922.7 1593.58  7989.3 1617.15
#Mann= 20 ,-1 , 0
  -838.2     .07       0  -304.4     .05       0  -152.4     .07       0
    64.3     .12       0   115.6     .07       0   358.8     .05       0
  1172.8     .07       0  1602.3     .05       0  1913.4     .07       0
  2681.4     .05       0  2965.2     .07       0  3602.2     .07       0
  4351.8     .05       0  4546.6     .07       0  4989.8     .04       0
  5051.2     .07       0  5191.4     .05       0    6182     .08       0
  6280.5     .05       0  6922.7     .07       0
#XS Ineff= 2 ,-1
    2000 3076.92 1530.69 3076.92 4490.84 1514.71
Permanent Ineff=
       F       F
Bank Sta=4989.8,5051.2
XS Rating Curve= 0 ,0
Exp/Cntr=0.3,0.1

Type RM Length L Ch R = 1 ,2134666 ,5331,5331,5331
BEGIN DESCRIPTION:
Guadalupe River - 140
END DESCRIPTION:
XS GIS Cut Line= 6
      1951181.87     13895447.07      1951151.51      13892126.8
      1951335.21     13891060.36      1951377.98     13890812.23
      1951487.51     13890345.08      1950349.96     13887820.05
#Sta/Elev= 30
   622.5 1616.78     637 1616.21   989.2  1589.8  1379.9 1560.06  1676.1 1545.08
  2521.1 1532.09  2867.2 1531.86  3396.5 1523.78  4113.6 1512.11  4585.6 1513.69
  4766.7 1500.51  4837.7 1483.13    4929 1485.48  4991.7 1479.25  5025.1 1484.54
  5107.5 1483.08  5158.3 1492.38  5234.2  1527.6  5243.6 1534.45  5261.7 1563.99
  5625.8 1554.82  5806.7 1538.38  5993.3 1533.55  6200.4 1547.65  6454.9 1566.74
  7244.8 1596.44  7525.4 1607.05  7826.8 1618.11  8108.2 1624.26  8526.1 1630.62
#Mann= 19 ,-1 , 0
   622.5     .07       0     637     .05       0   989.2     .07       0
  1379.9     .07       0  1676.1     .05       0  2521.1     .05       0
  2867.2     .07       0  3396.5     .05       0  4113.6     .07       0
    4929     .04       0  5025.1     .12       0  5158.3     .12       0
  5625.8     .05       0  5806.7     .12       0  6200.4     .07       0
  7244.8     .07       0  7525.4     .12       0  7826.8     .05       0
  8108.2     .12       0
Bank Sta=4929,5025.1
XS Rating Curve= 0 ,0
Exp/Cntr=0.3,0.1

Type RM Length L Ch R = 1 ,2129335 ,104,104,104
BEGIN DESCRIPTION:
Guadalupe River - 139
END DESCRIPTION:
XS GIS Cut Line= 4
      1954938.25     13896432.59      1955827.25     13892139.16
      1955861.98     13890585.34      1955823.68     13887409.59
#Sta/Elev= 30
   199.5 1609.98   509.4 1592.47  1198.7 1595.18  1344.2 1579.88  1407.3 1567.78
    1545 1532.44  1632.2 1528.65  1932.1 1522.81  2119.4 1520.58  2919.6 1520.11
  3403.7 1510.32    3708 1509.99  4119.2  1509.1  4678.8 1503.26  4788.2 1499.55
  4818.2 1489.86  4827.4 1480.48  4829.2 1478.18  5069.2 1480.48    5267 1489.79
  5740.6 1507.71  5879.4 1510.59  6174.4 1518.09  6578.9 1515.07  6722.5 1514.97
  7968.7 1513.42  8508.7 1520.59  8685.4 1531.25    8918  1536.8  9314.2 1542.86
#Mann= 20 ,-1 , 0
   199.5     .07       0   509.4     .07       0  1407.3     .07       0
  1632.2     .05       0  1932.1     .07       0  2119.4     .05       0
  3403.7      .1       0    3708     .05       0  4119.2     .05       0
  4678.8     .07       0  4827.4     .05       0  5069.2     .12       0
    5267     .05       0  5740.6     .05       0  5879.4     .07       0
  6174.4     .07       0  6578.9     .05       0  6722.5     .07       0
  8685.4     .07       0    8918     .05       0
Bank Sta=4827.4,5069.2
XS Rating Curve= 0 ,0
Exp/Cntr=0.3,0.1

Type RM Length L Ch R = 1 ,2129231 ,4421,4421,4421
BEGIN DESCRIPTION:
Guadalupe River - 138.5
END DESCRIPTION:
XS GIS Cut Line= 5
      1955044.01     13896453.04      1955891.82     13892140.97
      1955935.22     13891800.25      1955952.58     13891144.87
      1955913.52     13887414.38
#Sta/Elev= 30
   173.1 1608.82   426.6 1598.24   588.9 1585.06   748.7  1586.6    1038 1597.05
    1231 1594.98  1300.2 1585.76  1416.5 1563.59  1526.6 1534.46  1595.8 1526.14
    2071 1517.62  2893.5 1518.23  3488.8 1509.54  3688.1 1509.99  4694.7 1503.15
  4755.2 1492.38  4775.4  1472.8  4777.2  1470.5  5017.2  1472.8  5120.5 1475.81
    5264 1490.16  5715.7 1509.07  5864.6 1512.16  6159.9 1523.44  6553.5 1515.62
  6717.3 1514.13  7956.8 1513.65  8603.5 1529.11  8759.2 1532.72  9297.5  1542.9
#Mann= 20 ,-1 , 0
   173.1     .07       0   426.6     .12       0   748.7     .07       0
  1300.2     .05       0  1416.5     .07       0  1595.8     .05       0
  2893.5     .07       0  3488.8     .08       0  3688.1     .05       0
  4775.4     .05       0  5017.2     .07       0  5120.5     .08       0
    5264     .05       0  5715.7     .05       0  5864.6     .07       0
  6159.9     .12       0  6553.5     .05       0  6717.3     .07       0
  8603.5     .05       0  8759.2     .05       0
Bank Sta=4775.4,5017.2
XS Rating Curve= 0 ,0
Exp/Cntr=0.3,0.1

Type RM Length L Ch R = 1 ,2124810 ,4411,4411,4411
BEGIN DESCRIPTION:
Guadalupe River - 138
END DESCRIPTION:
XS GIS Cut Line= 4
      1960135.16     13895184.81       1959892.1     13892788.95
      1958607.38     13891087.56      1957093.31      13887573.8
#Sta/Elev= 30
  1962.5 1589.98  2210.2 1551.24  2334.2 1559.77  2384.5 1547.22  2533.1 1538.07
  2963.3 1518.45  4022.4 1511.16  4260.1 1509.87  4430.6 1509.83  4850.5 1507.19
  4921.2  1471.1  4935.1 1460.74  4974.4 1458.44  5035.7 1468.99  5091.9 1475.08
  5150.2 1467.59  5685.1 1496.83  6190.4 1501.47  6379.8 1501.93  7001.2 1514.36
  7435.6 1525.32  7699.1 1536.65    7870 1533.76  8304.3 1524.34  8446.9 1522.74
  8609.3 1520.84  9558.8 1524.32  9973.6 1531.21 10272.6 1532.95 10328.7 1532.71
#Mann= 20 ,-1 , 0
  1962.5     .07       0  2533.1     .12       0  2963.3     .07       0
  4022.4     .05       0  4260.1     .07       0  4430.6     .05       0
  4921.2     .04       0  5035.7     .05       0  6190.4     .07       0
  6379.8     .05       0  7001.2     .05       0  7435.6     .05       0
  7699.1     .08       0    7870     .05       0  8304.3     .08       0
  8446.9     .05       0  8609.3     .07       0  9558.8     .07       0
  9973.6     .05       0 10272.6     .12       0
Bank Sta=4921.2,5035.7
XS Rating Curve= 0 ,0
Exp/Cntr=0.3,0.1

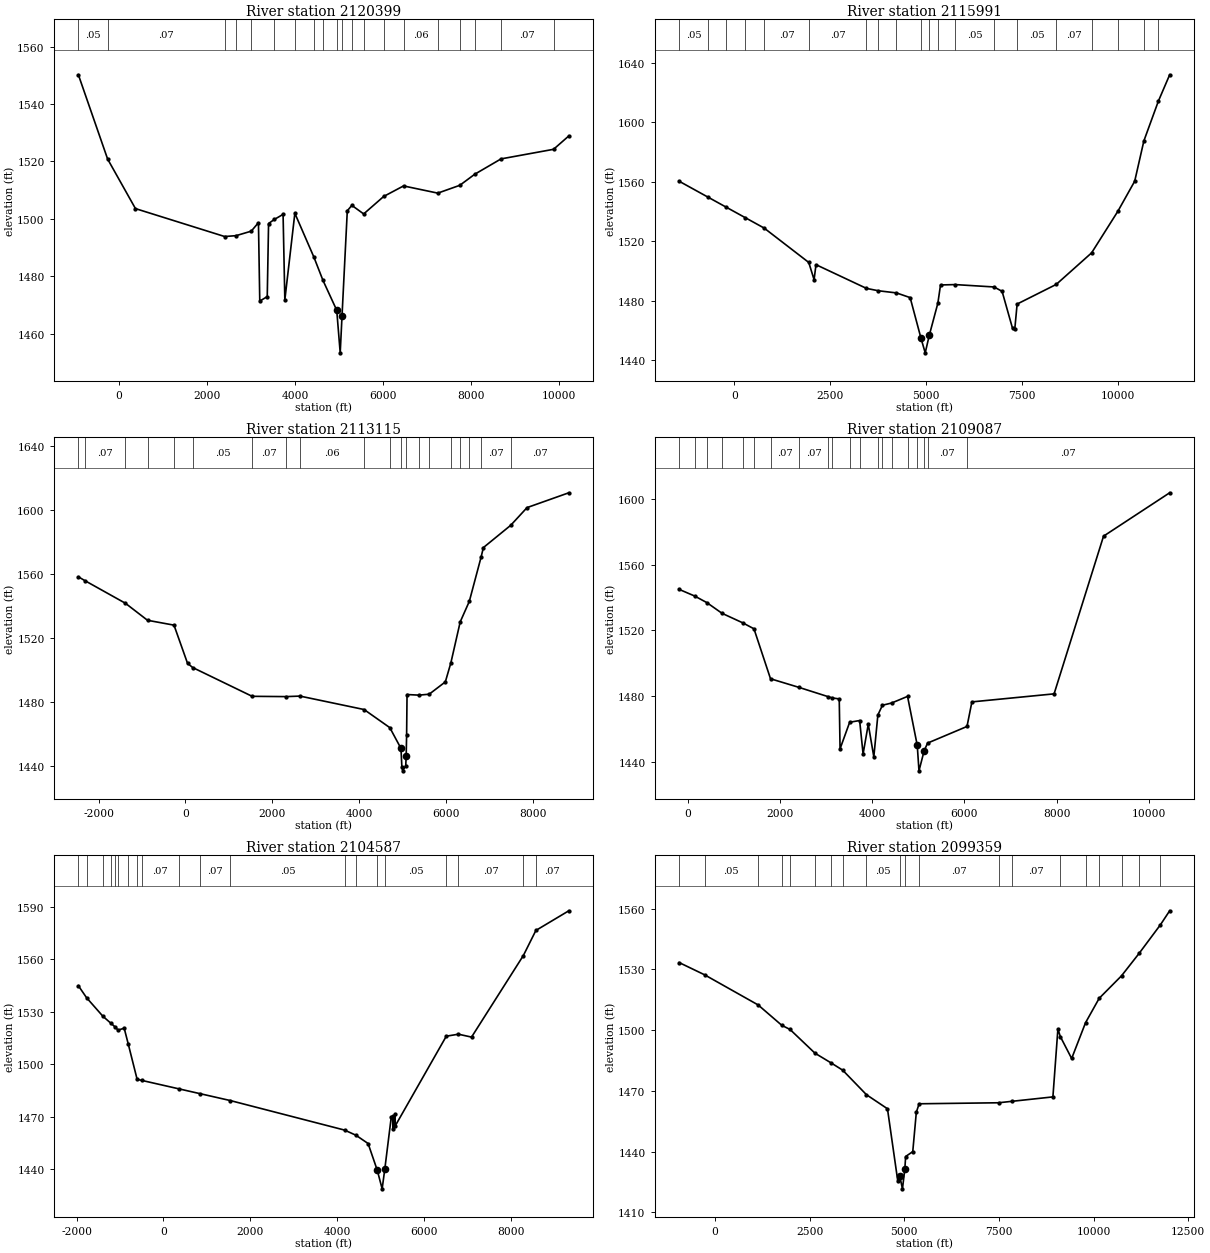
Type RM Length L Ch R = 1 ,2120399 ,4408,4408,4408
BEGIN DESCRIPTION:
Guadalupe River - 137
END DESCRIPTION:
XS GIS Cut Line= 6
      1960947.47     13895178.04      1962187.09     13893303.87
      1962183.89     13892878.96       1962073.4     13889567.45
      1962065.42     13889328.83      1957509.98     13887434.94
#Sta/Elev= 30
  -926.2 1550.17  -260.5 1520.79   372.3 1503.54  2401.4 1493.81  2661.1 1494.11
  3006.6 1495.68  3170.5 1498.64  3200.5 1471.32  3370.6 1472.87  3400.6 1498.34
  3532.6 1499.77  3730.8 1501.53  3770.8 1471.73  3998.5 1501.91  4431.4 1486.65
  4638.1 1478.54  4951.5 1468.11  5030.4 1453.28  5071.6 1466.09  5191.6 1502.77
  5294.9 1504.67  5564.5 1501.68  6019.8 1507.77    6471 1511.44  7250.1 1508.93
  7750.5 1511.65  8092.9 1515.53  8689.3 1520.86  9883.8  1524.2 10231.3 1528.86
#Mann= 20 ,-1 , 0
  -926.2     .05       0  -260.5     .07       0  2401.4     .05       0
  2661.1     .12       0  3006.6     .06       0  3532.6     .06       0
  3998.5     .06       0  4431.4     .06       0  4638.1     .07       0
  4951.5     .04       0  5071.6     .07       0  5294.9     .07       0
  5564.5     .05       0  6019.8     .12       0    6471     .06       0
  7250.1     .05       0  7750.5     .05       0  8092.9     .07       0
  8689.3     .07       0  9883.8     .12       0
Bank Sta=4951.5,5071.6
XS Rating Curve= 0 ,0
Exp/Cntr=0.3,0.1

Type RM Length L Ch R = 1 ,2115991 ,2876,2876,2876
BEGIN DESCRIPTION:
Guadalupe River - 136
END DESCRIPTION:
XS GIS Cut Line= 6
       1965947.5     13895247.43      1966182.15     13891129.72
      1965830.24     13889545.76      1964724.95     13888801.02
      1963067.58     13887272.28      1961399.45     13884241.54
#Sta/Elev= 30
 -1436.8 1560.33  -692.9 1549.76    -205 1542.83   286.8 1535.85   778.5 1528.87
  1942.1 1505.77  2081.3 1494.18  2131.4 1504.26  3448.3 1488.31    3757 1486.73
  4230.8 1485.27  4587.8 1482.11  4870.2 1454.81  4980.7 1444.98  5086.1 1456.68
  5310.7 1478.39    5380 1490.62  5763.4 1490.87    6777 1489.27  6986.3 1486.34
  7258.8 1461.44  7318.6 1461.23  7378.6 1477.78  8399.2 1490.99    9322 1512.21
 10007.7  1540.2 10446.1 1560.38 10685.5 1587.48 11064.5 1614.27 11358.6 1631.94
#Mann= 20 ,-1 , 0
 -1436.8     .05       0  -692.9     .05       0    -205     .07       0
   286.8     .12       0   778.5     .07       0  1942.1     .07       0
  3448.3     .05       0    3757     .07       0  4230.8     .05       0
  4870.2     .04       0  5086.1     .05       0  5310.7     .05       0
  5763.4     .05       0    6777     .07       0  7378.6     .05       0
  8399.2     .07       0    9322     .07       0 10007.7     .12       0
 10685.5     .07       0 11064.5     .12       0
Bank Sta=4870.2,5086.1
XS Rating Curve= 0 ,0
Exp/Cntr=0.3,0.1

Type RM Length L Ch R = 1 ,2113115 ,4028,4028,4028
BEGIN DESCRIPTION:
Guadalupe River - 135
END DESCRIPTION:
XS GIS Cut Line= 6
      1966259.98     13895073.87      1967302.92     13891594.56
      1967224.44     13889794.55      1967178.17     13887221.44
      1967169.59      13886982.4      1968516.96     13884240.46
#Sta/Elev= 30
 -2468.4 1558.32 -2306.8 1555.76 -1383.9 1541.79  -875.3 1531.16  -264.9 1528.12
    46.4  1504.3   165.2 1501.63  1535.6 1483.63  2317.4 1483.45  2638.6 1483.77
  4115.7 1475.37  4708.2 1464.05  4965.5 1451.06  4986.3 1439.45  5006.4 1437.05
  5075.5 1440.25  5085.5 1446.38  5095.5 1459.29  5105.5 1484.75  5379.4 1484.37
  5615.6 1484.95    5988 1492.65  6115.7 1504.58  6330.3 1530.14  6540.3 1542.98
  6810.5  1570.5  6864.7  1576.6  7494.9 1590.54  7870.5 1601.59  8833.4 1610.86
#Mann= 20 ,-1 , 0
 -2468.4     .07       0 -2306.8     .07       0 -1383.9     .07       0
  -875.3     .12       0  -264.9     .07       0   165.2     .05       0
  1535.6     .07       0  2317.4     .05       0  2638.6     .06       0
  4115.7     .05       0  4708.2     .05       0  4965.5     .04       0
  5085.5     .05       0  5379.4     .07       0  5615.6     .05       0
  6115.7     .12       0  6330.3     .05       0  6540.3     .07       0
  6810.5     .07       0  7494.9     .07       0
Bank Sta=4965.5,5085.5
XS Rating Curve= 0 ,0
Exp/Cntr=0.3,0.1

Type RM Length L Ch R = 1 ,2109087 ,4500,4500,4500
BEGIN DESCRIPTION:
Guadalupe River - 134
END DESCRIPTION:
XS GIS Cut Line= 6
      1970912.78     13894969.71      1970060.33     13892234.57
      1969926.21     13890283.21      1969945.16     13888942.52
      1969870.78     13888236.58      1969662.77     13884483.58
#Sta/Elev= 30
    -183 1544.89   150.1 1540.89   416.8 1536.86   743.7  1530.4  1194.9 1524.58
  1436.9 1520.98  1795.5 1490.65  2419.8 1485.36  3035.5 1479.87  3134.4 1479.01
    3285 1478.42  3302.9 1448.13  3511.3 1464.26  3727.3 1465.29    3802 1444.99
  3914.4 1463.05  4034.7 1443.26  4122.5 1468.67  4221.4 1474.58    4419 1475.92
  4765.8 1479.95  4976.1 1450.23  5013.5 1434.76  5126.1 1447.01  5200.6 1451.61
  6054.4  1461.7  6160.6 1476.61    7942 1481.49  9013.7 1577.21 10447.3 1603.55
#Mann= 20 ,-1 , 0
    -183     .12       0   150.1     .07       0   416.8     .07       0
   743.7     .05       0  1194.9     .07       0  1436.9     .12       0
  1795.5     .07       0  2419.8     .07       0  3035.5     .05       0
  3134.4     .07       0  3511.3     .05       0  3727.3     .12       0
  4122.5     .05       0  4221.4     .07       0    4419     .05       0
  4765.8     .05       0  4976.1     .04       0  5126.1     .07       0
  5200.6     .07       0  6054.4     .07       0
Bank Sta=4976.1,5126.1
XS Rating Curve= 0 ,0
Exp/Cntr=0.3,0.1

Type RM Length L Ch R = 1 ,2104587 ,5228,5228,5228
BEGIN DESCRIPTION:
Guadalupe River - 133
END DESCRIPTION:
XS GIS Cut Line= 6
      1972232.23     13895039.08       1973254.1     13891296.07
      1973238.78     13888499.05      1973517.58     13887722.26
      1973562.79     13886818.44      1971676.68     13884622.47
#Sta/Elev= 30
 -1958.3 1544.89 -1769.2 1538.03 -1394.1 1527.46 -1210.9 1523.48 -1109.8 1521.29
 -1044.6 1519.53  -902.4 1520.62  -806.5 1511.34  -604.3 1491.39  -503.2 1490.82
   352.8 1485.99     838 1483.25    1541 1479.28  4176.9 1462.39  4438.2 1459.45
  4718.3 1454.72  4929.9 1439.41    5042 1428.82  5103.7  1440.2  5252.1 1469.88
  5282.9 1470.25  5288.9 1462.92    5339 1471.65  5344.3 1464.83  6520.3 1516.05
  6799.7 1517.19    7102 1515.53  8295.9 1562.14  8584.9 1576.48  9343.8 1587.72
#Mann= 20 ,-1 , 0
 -1958.3     .05       0 -1769.2     .07       0 -1394.1     .05       0
 -1210.9     .07       0 -1109.8     .05       0 -1044.6     .07       0
  -806.5     .07       0  -604.3     .05       0  -503.2     .07       0
   352.8     .05       0     838     .07       0    1541     .05       0
  4176.9     .07       0  4438.2     .05       0  4929.9     .04       0
  5103.7     .05       0  6520.3     .12       0  6799.7     .07       0
  8295.9     .05       0  8584.9     .07       0
Bank Sta=4929.9,5103.7
XS Rating Curve= 0 ,0
Exp/Cntr=0.3,0.1

Type RM Length L Ch R = 1 ,2099359 ,3810,3810,3810
BEGIN DESCRIPTION:
Guadalupe River - 132
END DESCRIPTION:
XS GIS Cut Line= 6
      1975843.33     13893511.34      1978039.09     13889381.33
      1978040.25     13889193.87       1977777.4     13888284.55
      1977039.55     13885890.84      1972544.69     13884761.33
#Sta/Elev= 30
  -942.3 1533.36  -273.9 1527.35  1141.5 1512.45    1765 1502.41  1984.1 1500.34
  2641.6 1488.64  3074.9 1483.75  3373.7 1480.25  4001.1 1468.14  4556.4 1461.19
    4828 1425.62  4879.1  1428.1  4952.3 1421.65  5015.2 1431.46  5036.1 1437.61
  5224.4 1440.03  5318.6 1459.49  5392.8 1463.65  7490.7 1464.15  7834.9 1464.85
  8925.3 1467.05    9057 1500.58  9121.2 1496.83  9420.2 1486.01  9786.6 1503.67
 10147.1 1515.73 10737.3 1526.85 11199.6 1537.87 11762.9    1552 12008.6 1558.95
#Mann= 20 ,-1 , 0
  -942.3     .07       0  -273.9     .05       0  1141.5     .07       0
    1765     .07       0  1984.1     .05       0  2641.6     .05       0
  3074.9     .07       0  3373.7     .05       0  4001.1     .05       0
  4879.1     .04       0  5015.2     .12       0  5392.8     .07       0
  7490.7     .05       0  7834.9     .07       0  9121.2     .05       0
  9786.6     .07       0 10147.1     .07       0 10737.3     .05       0
 11199.6     .07       0 11762.9     .07       0
Bank Sta=4879.1,5015.2
XS Rating Curve= 0 ,0
Exp/Cntr=0.3,0.1

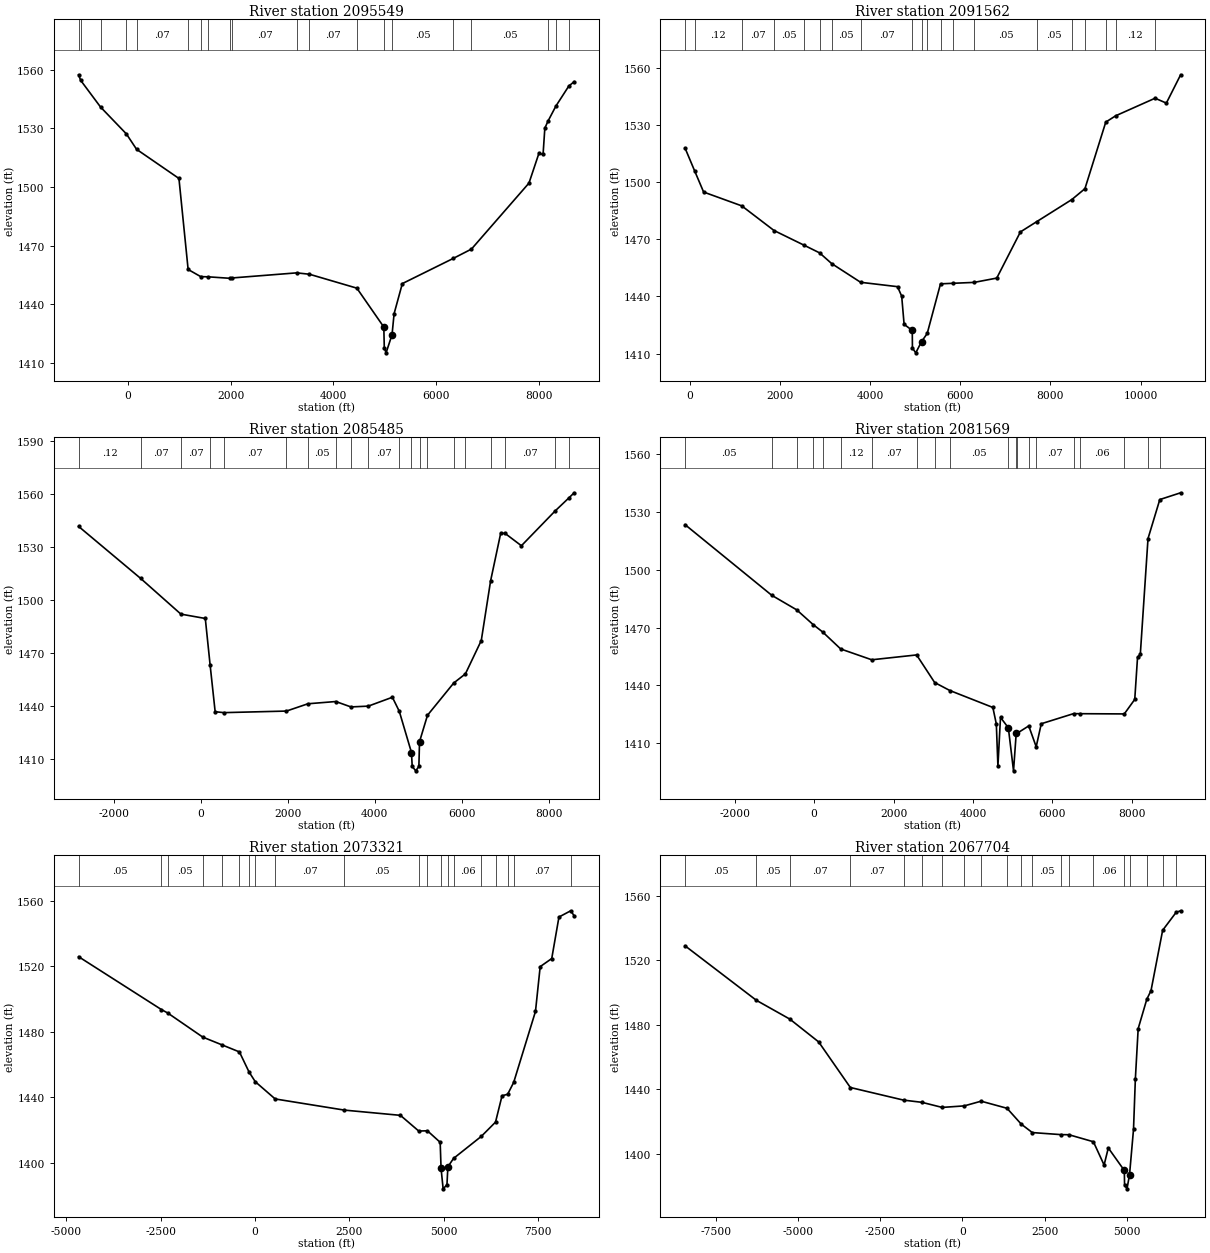
Type RM Length L Ch R = 1 ,2095549 ,3987,3987,3987
BEGIN DESCRIPTION:
Guadalupe River - 131
END DESCRIPTION:
XS GIS Cut Line= 6
      1980600.26     13894205.82      1981090.87      13892101.1
       1981122.2     13890823.48      1981135.17     13889857.83
      1981170.98     13887193.95      1981606.98     13884658.57
#Sta/Elev= 30
  -957.4  1557.4  -918.8 1554.59  -530.8 1540.88   -28.6 1527.14   170.2 1519.25
   994.4 1504.33  1173.1 1457.74  1417.4 1454.09  1568.9 1453.97  1987.9 1453.22
  2033.9 1453.41  3285.9 1456.01  3533.5  1455.3  4455.8 1448.18  4980.5 1428.28
  4989.8 1417.57  5024.6 1415.07  5140.5 1424.36  5180.5  1435.1  5340.5 1450.51
  6328.4 1463.36  6685.8 1468.18  7805.1 1501.97  7998.5  1517.2    8079 1516.61
  8113.3 1530.06    8175 1533.68  8328.7 1541.38  8580.5 1551.66  8684.2 1553.85
#Mann= 20 ,-1 , 0
  -957.4     .07       0  -918.8     .05       0  -530.8     .07       0
   -28.6     .12       0   170.2     .07       0  1173.1     .07       0
  1417.4     .05       0  1568.9     .07       0  1987.9     .06       0
  2033.9     .07       0  3285.9     .05       0  3533.5     .07       0
  4455.8     .05       0  4980.5     .04       0  5140.5     .05       0
  6328.4     .07       0  6685.8     .05       0    8175     .07       0
  8328.7     .07       0  8580.5     .05       0
Bank Sta=4980.5,5140.5
XS Rating Curve= 0 ,0
Exp/Cntr=0.3,0.1

Type RM Length L Ch R = 1 ,2091562 ,6077,6077,6077
BEGIN DESCRIPTION:
Guadalupe River - 130
END DESCRIPTION:
XS GIS Cut Line= 6
      1982475.27     13893928.01      1983748.34     13891045.74
      1984778.41     13888378.93      1985050.64     13887665.13
      1984994.42     13887540.19      1983169.86     13883893.56
#Sta/Elev= 30
  -102.1 1517.85   106.4 1506.11   308.4 1494.83  1154.4 1487.57  1869.6 1474.64
  2537.9  1466.9  2879.3 1462.91  3147.4 1457.29  3790.3 1447.45  4607.8 1445.16
  4700.7 1440.17  4754.3 1425.39  4935.3 1422.17  4938.8 1412.92  5013.2 1410.42
  5140.1 1416.27  5266.4 1420.58  5561.5 1446.64  5831.8 1446.92  6306.6  1447.4
  6808.6 1449.66  7333.4  1473.9  7697.8 1479.33  8473.8 1490.89    8764 1496.59
  9225.9 1531.54  9445.5 1534.86 10319.3 1544.08 10569.5 1541.52 10886.2 1556.39
#Mann= 20 ,-1 , 0
  -102.1     .12       0   106.4     .12       0  1154.4     .07       0
  1869.6     .05       0  2537.9     .05       0  2879.3     .07       0
  3147.4     .05       0  3790.3     .07       0  4935.3     .04       0
  5140.1     .12       0  5266.4     .05       0  5561.5     .07       0
  5831.8     .06       0  6306.6     .05       0  7697.8     .05       0
  8473.8     .06       0    8764     .07       0  9225.9     .07       0
  9445.5     .12       0 10319.3     .07       0
Bank Sta=4935.3,5140.1
XS Rating Curve= 0 ,0
Exp/Cntr=0.3,0.1

Type RM Length L Ch R = 1 ,2085485 ,3916,3916,3916
BEGIN DESCRIPTION:
Guadalupe River - 129
END DESCRIPTION:
XS GIS Cut Line= 3
      1983017.08     13896434.79      1985274.04      13895358.4
      1990898.52     13888449.31
#Sta/Elev= 30
 -2818.4 1541.72   -1389 1512.22    -464 1492.01      98 1489.54   209.6 1463.02
   324.9 1436.67   525.5 1436.15  1966.4 1437.04  2461.1 1441.18  3102.6 1442.45
  3450.6 1439.39  3851.2 1439.84  4405.6 1444.87  4564.1 1436.93  4845.1 1413.53
  4861.9 1405.65  4943.8 1403.15  5015.6 1405.65  5030.4 1419.67  5213.9 1434.67
  5817.9 1452.95  6086.9 1458.13  6452.4 1477.04  6666.4 1510.82  6899.8 1537.91
  7000.3 1537.78    7376 1530.78  8150.6 1550.45  8461.9 1557.73  8591.1 1560.81
#Mann= 20 ,-1 , 0
 -2818.4     .12       0   -1389     .07       0    -464     .07       0
   209.6     .05       0   525.5     .07       0  1966.4     .05       0
  2461.1     .05       0  3102.6     .07       0  3450.6     .05       0
  3851.2     .07       0  4564.1     .05       0  4845.1     .04       0
  5030.4    .035       0  5213.9     .05       0  5817.9     .07       0
  6086.9     .05       0  6666.4     .12       0  7000.3     .07       0
  8150.6     .12       0  8461.9     .07       0
Bank Sta=4845.1,5030.4
XS Rating Curve= 0 ,0
Exp/Cntr=0.3,0.1

Type RM Length L Ch R = 1 ,2081569 ,8248,8248,8248
BEGIN DESCRIPTION:
Guadalupe River - 128
END DESCRIPTION:
XS GIS Cut Line= 3
      1988225.41     13901122.32      1990586.54     13897441.73
      1991003.21     13889351.49
#Sta/Elev= 30
 -3247.1 1523.41 -1066.8 1486.75  -435.9 1479.15   -25.4 1471.54   216.9 1467.66
   669.2 1458.86  1451.2 1453.24  2580.6 1455.76  3034.7 1441.43  3416.9 1437.28
    4500 1428.48  4587.1 1419.89  4627.1 1398.06  4692.4 1423.31  4889.7 1417.91
  5020.1 1395.56  5087.7 1415.08  5118.4 1415.17  5403.4 1418.89  5590.5 1408.07
  5718.5 1420.02  6529.8 1425.26  6701.9 1425.24  7808.3 1425.12  8071.7 1432.66
  8141.8 1454.56  8211.8 1456.13  8405.4  1516.2  8702.3 1536.46  9226.7 1539.98
#Mann= 20 ,-1 , 0
 -3247.1     .05       0 -1066.8     .07       0  -435.9     .05       0
   -25.4     .07       0   216.9     .05       0   669.2     .12       0
  1451.2     .07       0  2580.6     .07       0  3034.7     .07       0
  3416.9     .05       0  4889.7     .04       0  5087.7     .12       0
  5118.4     .07       0  5403.4     .05       0  5590.5     .07       0
  6529.8     .05       0  6701.9     .06       0  7808.3     .05       0
  8405.4     .05       0  8702.3     .05       0
Bank Sta=4889.7,5087.7
XS Rating Curve= 0 ,0
Exp/Cntr=0.3,0.1

Type RM Length L Ch R = 1 ,2073321 ,5617,5617,5617
BEGIN DESCRIPTION:
Guadalupe River - 127
END DESCRIPTION:
XS GIS Cut Line= 4
      1988329.63     13901226.41      1989996.27     13898934.78
      1993989.32     13897302.84        1996211.     13891748.66
#Sta/Elev= 30
 -4670.8 1525.75 -2476.3 1493.52 -2311.6 1491.46 -1381.8 1476.75  -870.4    1472
  -410.7 1467.72  -156.8 1455.54     9.4 1449.57   536.6 1439.06  2370.4 1432.26
  3854.8 1429.07  4340.2 1419.51    4570 1419.66  4908.2 1412.64  4931.8  1396.7
  4986.8 1384.28  5087.9 1386.78  5112.3 1397.72  5262.8 1402.83  5997.1 1416.24
  6374.6 1424.94  6547.4 1441.01  6696.1 1441.92  6856.3 1449.17  7433.3  1492.4
  7557.7 1519.69  7864.1 1524.63  8055.2 1549.93    8367 1553.74  8458.5 1550.67
#Mann= 20 ,-1 , 0
 -4670.8     .05       0 -2476.3     .07       0 -2311.6     .05       0
 -1381.8     .12       0  -870.4     .07       0  -410.7     .05       0
  -156.8     .07       0     9.4     .05       0   536.6     .07       0
  2370.4     .05       0  4340.2     .07       0    4570     .05       0
  4931.8     .04       0  5112.3     .05       0  5262.8     .06       0
  5997.1     .07       0  6374.6     .07       0  6696.1     .12       0
  6856.3     .07       0    8367     .07       0
Bank Sta=4931.8,5112.3
XS Rating Curve= 0 ,0
Exp/Cntr=0.3,0.1

Type RM Length L Ch R = 1 ,2067704 ,7572,7572,7572
BEGIN DESCRIPTION:
Guadalupe River - 126
END DESCRIPTION:
XS GIS Cut Line= 5
      1988433.77     13901434.77      1990065.71     13899247.28
      1997114.32      13896295.9      1998850.43     13896157.01
      2001107.39     13894247.27
#Sta/Elev= 30
 -8429.5  1529.1 -6261.3 1495.25 -5245.2 1483.59 -4367.6 1469.41 -3404.4 1441.09
 -1787.9 1433.26 -1228.1 1431.88  -612.4 1428.72    60.7 1429.67   572.2 1432.59
    1360 1428.18  1793.2 1418.31  2128.7 1413.09  2996.6 1411.82  3244.3 1411.74
  3986.5 1407.39    4312 1392.93  4439.5 1403.54  4926.8 1389.54  4934.2 1380.63
  5008.1 1378.13  5085.5 1386.95  5206.4 1415.09  5262.4 1446.33  5348.1 1477.66
  5611.6 1495.98  5738.1 1501.25  6092.3 1538.77  6503.4 1549.94  6639.4 1550.89
#Mann= 20 ,-1 , 0
 -8429.5     .05       0 -6261.3     .05       0 -5245.2     .07       0
 -3404.4     .07       0 -1787.9     .05       0 -1228.1     .05       0
  -612.4     .07       0    60.7     .07       0   572.2     .05       0
    1360     .07       0  1793.2     .07       0  2128.7     .05       0
  2996.6     .06       0  3244.3     .05       0  3986.5     .06       0
  4926.8     .04       0  5085.5     .05       0  5611.6     .07       0
  6092.3     .07       0  6503.4     .05       0
Bank Sta=4926.8,5085.5
XS Rating Curve= 0 ,0
Exp/Cntr=0.3,0.1

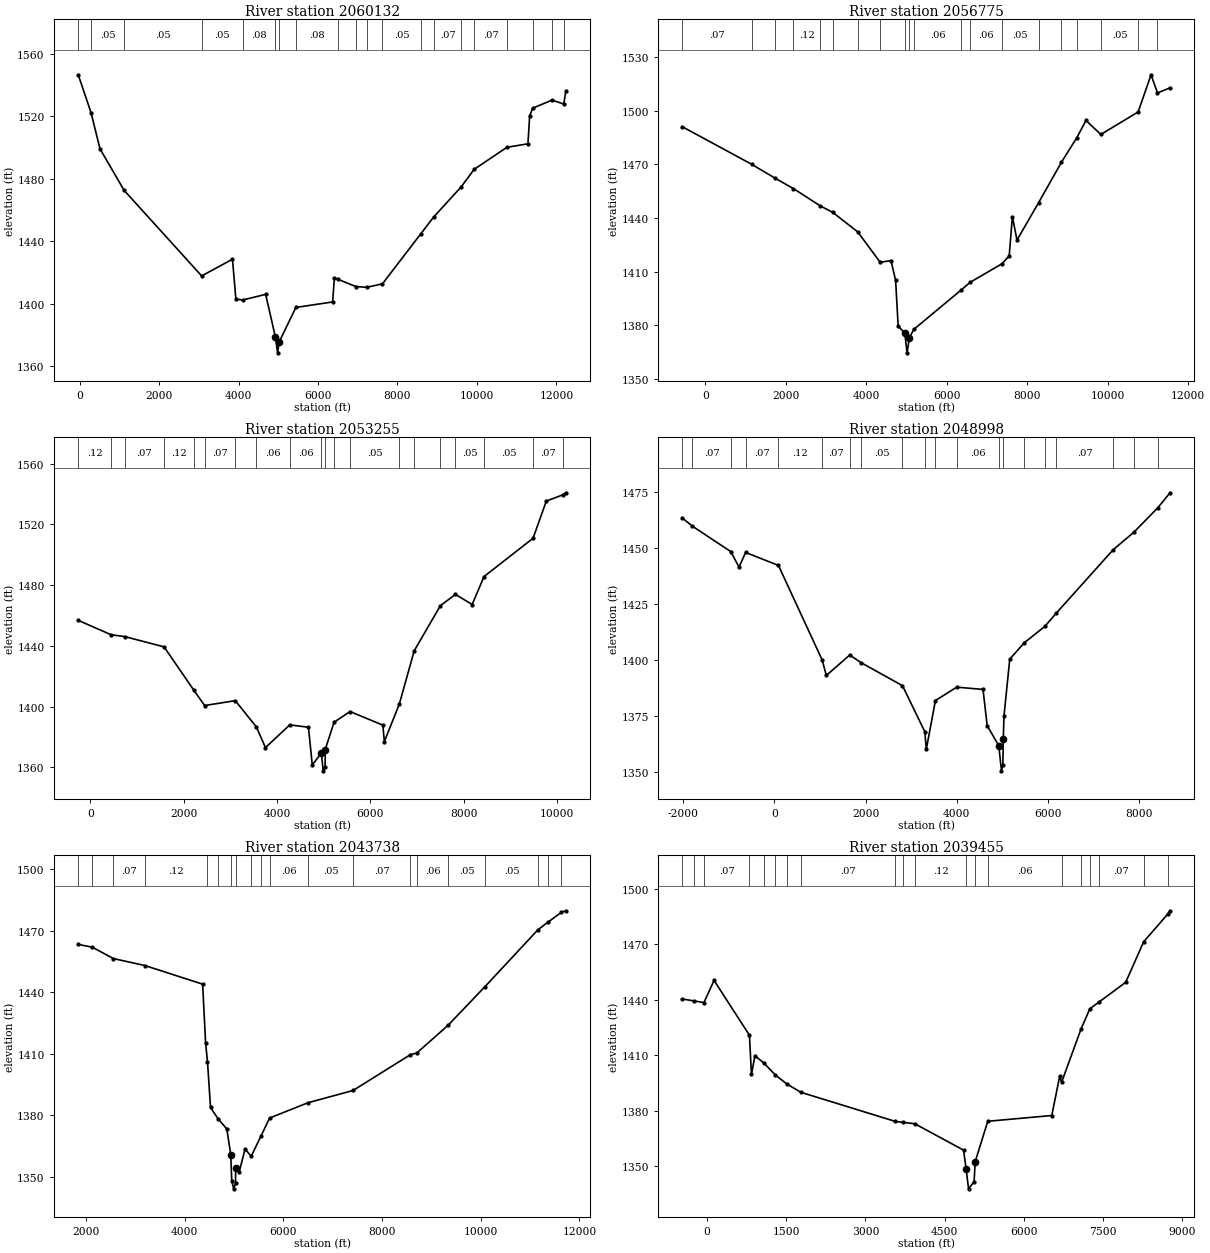
Type RM Length L Ch R = 1 ,2060132 ,3357,3357,3357
BEGIN DESCRIPTION:
Guadalupe River - 125
END DESCRIPTION:
XS GIS Cut Line= 3
      2000760.17     13904837.54      2003468.49     13897684.78
      2001177.67     13893658.49
#Sta/Elev= 30
   -39.6 1546.56   281.8 1522.39   508.4  1499.2  1113.6 1472.69  3068.1  1417.9
  3844.6 1428.57  3930.2 1403.02  4109.4 1402.53    4680 1406.12  4924.6 1378.89
  4981.9  1368.7  5020.8 1375.67  5440.6 1397.73  6366.6 1401.25  6410.9 1416.72
  6512.2 1415.62  6951.2 1411.11  7227.7 1410.61    7622 1412.87  8587.4 1444.85
    8913 1455.65  9604.4 1474.87  9927.8 1486.02 10756.6 1500.17 11285.2 1502.42
 11328.4 1520.39 11408.4 1525.24 11889.8 1530.34 12186.6 1527.89 12241.1 1536.16
#Mann= 20 ,-1 , 0
   -39.6     .12       0   281.8     .05       0  1113.6     .05       0
  3068.1     .05       0  4109.4     .08       0  4924.6     .04       0
  5020.8     .05       0  5440.6     .08       0  6512.2     .05       0
  6951.2     .08       0  7227.7     .08       0    7622     .05       0
  8587.4     .05       0    8913     .07       0  9604.4     .07       0
  9927.8     .07       0 10756.6     .07       0 11408.4     .07       0
 11889.8     .07       0 12186.6     .05       0
Bank Sta=4924.6,5020.8
XS Rating Curve= 0 ,0
Exp/Cntr=0.3,0.1

Type RM Length L Ch R = 1 ,2056775 ,3520,3520,3520
BEGIN DESCRIPTION:
Guadalupe River - 124
END DESCRIPTION:
XS GIS Cut Line= 5
      2005308.77     13904247.28      2005274.04     13901538.95
      2005933.77     13900288.95      2002808.77     13896087.56
      2001385.16     13893726.45
#Sta/Elev= 30
  -567.4 1491.09  1149.7 1470.12  1740.2 1462.23  2189.5 1456.48  2862.5  1446.7
  3164.1 1443.19  3787.8 1432.21  4346.5 1415.16  4614.5 1416.14  4729.3 1405.03
  4793.3  1379.3  4956.6 1375.65  5014.4 1364.43  5071.3 1372.83  5179.5 1377.53
  6364.5 1399.78  6584.3 1403.99  7376.3  1414.4  7551.3 1418.82  7630.6 1440.69
  7745.3 1427.64  8281.1 1448.54  8850.6 1471.29  9229.3  1484.9  9459.3 1494.67
  9827.2 1486.77 10755.3 1499.41 11075.1 1520.23 11235.4 1510.03 11547.8 1512.94
#Mann= 20 ,-1 , 0
  -567.4     .07       0  1149.7     .07       0  1740.2     .05       0
  2189.5     .12       0  2862.5     .05       0  3164.1     .07       0
  3787.8     .07       0  4346.5     .07       0  4956.6     .04       0
  5071.3     .12       0  5179.5     .06       0  6364.5     .07       0
  6584.3     .06       0  7376.3     .05       0  8281.1     .07       0
  8850.6     .12       0  9229.3     .07       0  9827.2     .05       0
 10755.3     .05       0 11235.4     .07       0
Bank Sta=4956.6,5071.3
XS Rating Curve= 0 ,0
Exp/Cntr=0.3,0.1

Type RM Length L Ch R = 1 ,2053255 ,4257,4257,4257
BEGIN DESCRIPTION:
Guadalupe River - 123
END DESCRIPTION:
XS GIS Cut Line= 4
      2005447.67      13901504.2      2006836.54     13898830.62
      2005482.38     13893275.06      2004301.81     13892025.05
#Sta/Elev= 30
  -261.7 1456.84   443.1 1447.37   734.9 1446.17  1577.5 1439.39  2208.7 1411.15
  2446.1 1400.76    3104 1403.97  3556.7  1386.6  3750.1 1373.06  4270.9 1388.02
  4671.3 1386.47  4753.7 1361.61  4949.3 1369.55  4987.3 1357.76  5028.3 1360.46
  5031.6 1371.79    5220 1389.76  5563.3 1396.81  6266.7 1387.82  6297.6 1377.03
  6617.5  1401.6    6939 1436.87  7498.3 1466.49  7820.8 1473.95  8179.9 1467.27
  8433.4 1485.67  9484.2 1510.88  9769.1 1535.41 10121.5 1539.47 10188.7 1540.85
#Mann= 20 ,-1 , 0
  -261.7     .12       0   443.1     .05       0   734.9     .07       0
  1577.5     .12       0  2208.7     .12       0  2446.1     .07       0
    3104     .06       0  3556.7     .06       0  4270.9     .06       0
  4949.3     .04       0  5031.6     .07       0    5220     .05       0
  5563.3     .05       0  6617.5     .12       0    6939     .07       0
  7498.3     .07       0  7820.8     .05       0  8433.4     .05       0
  9484.2     .07       0 10121.5     .12       0
Bank Sta=4949.3,5031.6
XS Rating Curve= 0 ,0
Exp/Cntr=0.3,0.1

Type RM Length L Ch R = 1 ,2048998 ,5260,5260,5260
BEGIN DESCRIPTION:
Guadalupe River - 122
END DESCRIPTION:
XS GIS Cut Line= 3
      2005378.21       13901782.      2007357.38     13898587.56
      2012079.59     13893483.41
#Sta/Elev= 30
 -2022.2 1463.33 -1804.7 1459.75  -959.3 1448.39  -778.8 1441.49  -632.9 1448.01
    87.4 1442.22  1048.8 1400.02  1138.8 1393.16  1653.2 1402.27  1907.5 1398.82
  2811.4 1388.62  3302.5  1368.1  3334.9 1360.27  3535.3 1381.98  4003.4 1387.96
  4580.5 1386.94  4672.4  1370.8    4927 1361.85  4986.2 1350.65  5016.5 1353.35
  5026.2 1364.64  5040.4 1374.92    5168 1400.45  5488.3 1407.77  5938.8 1415.04
  6187.1 1420.89  7441.3 1449.26  7890.9 1456.96  8420.3 1467.93  8689.2 1474.61
#Mann= 20 ,-1 , 0
 -2022.2     .05       0 -1804.7     .07       0  -959.3     .05       0
  -632.9     .07       0    87.4     .12       0  1048.8     .07       0
  1653.2     .07       0  1907.5     .05       0  2811.4     .12       0
  3302.5     .06       0  3535.3     .05       0  4003.4     .06       0
    4927     .04       0  5026.2     .05       0  5488.3     .07       0
  5938.8     .07       0  6187.1     .07       0  7441.3     .05       0
  7890.9     .05       0  8420.3     .07       0
Bank Sta=4927,5026.2
XS Rating Curve= 0 ,0
Exp/Cntr=0.3,0.1

Type RM Length L Ch R = 1 ,2043738 ,4283,4283,4283
BEGIN DESCRIPTION:
Guadalupe River - 121
END DESCRIPTION:
XS GIS Cut Line= 4
      2010100.45     13902858.38      2011419.88      13900983.4
      2011419.88     13896261.17       2013050.9      13893901.4
#Sta/Elev= 30
  1841.3 1463.33    2125 1461.98  2555.3 1456.42  3191.4 1453.04  4362.4 1443.96
  4422.4 1415.32    4461 1406.14  4522.4 1383.86  4677.4 1378.29  4852.4 1373.36
  4932.4 1360.92  4952.4 1348.07  4992.4 1344.21  5028.9 1346.91  5032.4 1354.45
  5102.4 1352.31  5222.4 1363.62  5346.3 1360.05  5543.1 1369.87  5721.1 1378.73
  6498.9 1386.19  7410.8 1392.14  8574.4 1409.62  8701.1 1410.37  9338.7 1423.97
 10086.6  1442.8 11161.6 1470.56 11354.3 1474.03 11631.9 1478.97 11724.8 1479.72
#Mann= 20 ,-1 , 0
  1841.3     .05       0    2125     .12       0  2555.3     .07       0
  3191.4     .12       0    4461     .05       0  4677.4     .07       0
  4932.4     .04       0  5032.4     .07       0  5346.3     .12       0
  5543.1     .07       0  5721.1     .06       0  6498.9     .05       0
  7410.8     .07       0  8574.4     .05       0  8701.1     .06       0
  9338.7     .05       0 10086.6     .05       0 11161.6     .07       0
 11354.3     .05       0 11631.9     .07       0
Bank Sta=4932.4,5032.4
XS Rating Curve= 0 ,0
Exp/Cntr=0.3,0.1

Type RM Length L Ch R = 1 ,2039455 ,3024,3024,3024
BEGIN DESCRIPTION:
Guadalupe River - 120
END DESCRIPTION:
XS GIS Cut Line= 4
      2012834.89     13903159.29      2014537.78     13900022.39
      2014746.91     13895839.82       2015493.8     13894555.16
#Sta/Elev= 30
  -469.4 1440.28  -249.8 1439.24     -61 1438.34   130.5 1450.33   801.1 1420.71
   839.6 1399.49   905.2 1409.59  1070.9  1405.8  1291.1 1399.25  1511.2 1394.32
  1780.1 1389.82    3566 1374.12  3714.6 1373.61  3936.7 1372.85  4859.5 1358.59
  4909.6 1348.18  4954.3 1337.68  5059.7  1341.6  5079.8 1352.37  5318.8  1374.2
  6531.6 1377.31  6681.8 1398.56  6717.9 1395.28  7088.9 1424.27  7254.9 1435.06
  7421.9 1438.52  7932.9 1449.31  8273.7 1471.24  8736.9 1486.41  8773.7 1487.96
#Mann= 20 ,-1 , 0
  -469.4     .07       0  -249.8     .12       0     -61     .07       0
   801.1     .05       0  1070.9     .05       0  1291.1     .07       0
  1511.2     .05       0  1780.1     .07       0    3566     .07       0
  3714.6     .05       0  3936.7     .12       0  4909.6     .04       0
  5079.8     .12       0  5318.8     .06       0  6717.9     .05       0
  7088.9     .12       0  7254.9     .12       0  7421.9     .07       0
  8273.7     .12       0  8736.9     .05       0
Bank Sta=4909.6,5079.8
XS Rating Curve= 0 ,0
Exp/Cntr=0.3,0.1