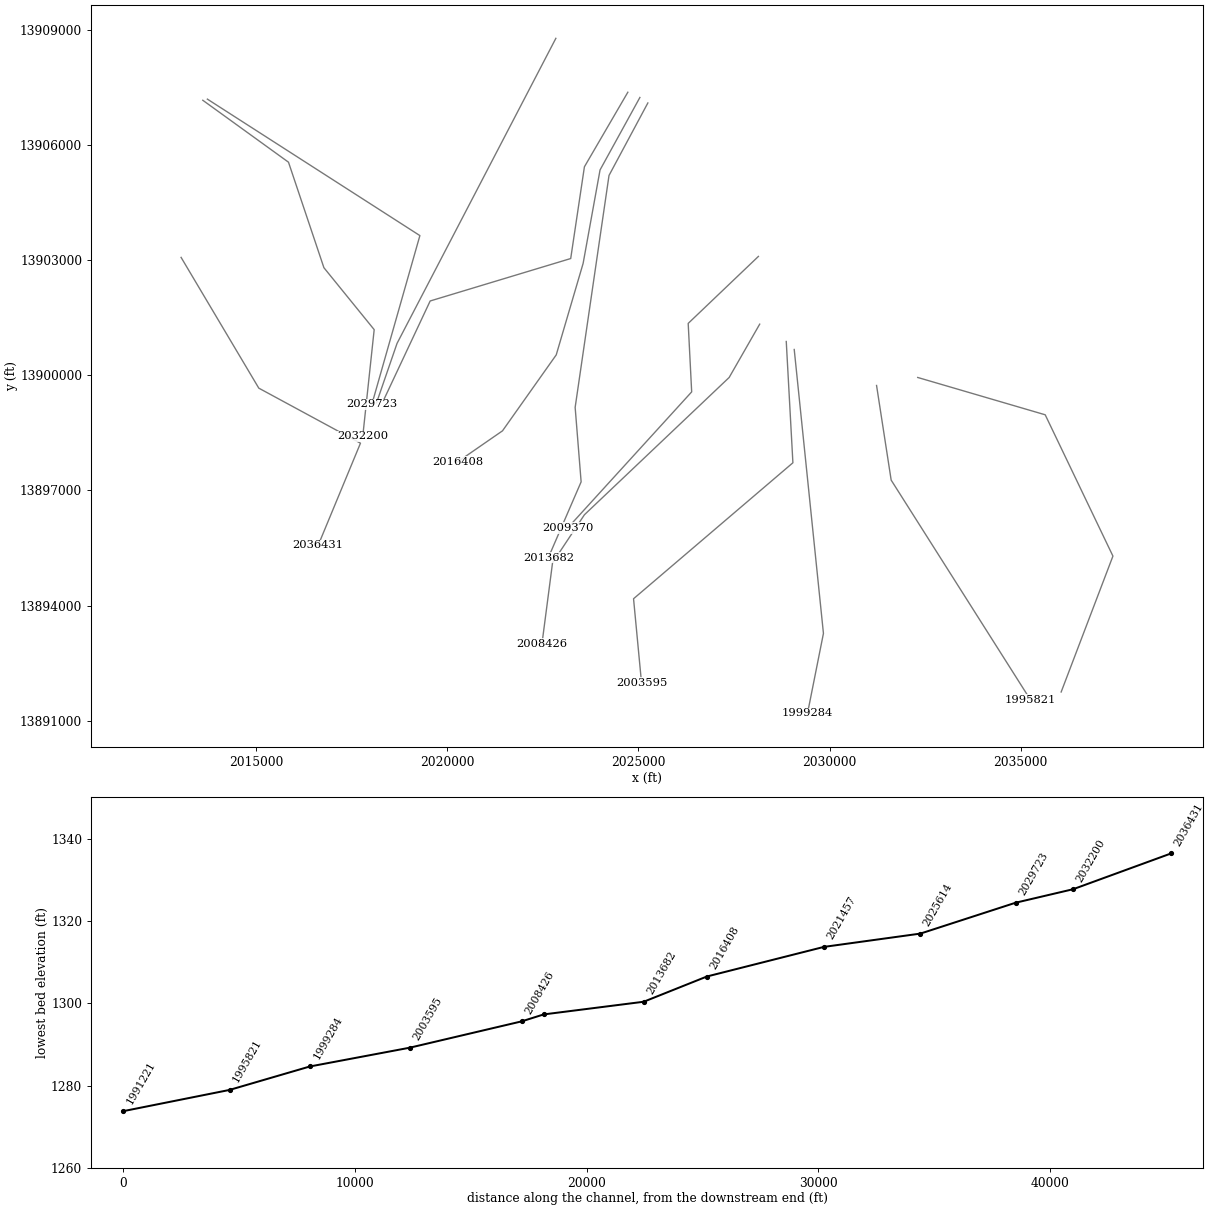
HEC-RAS study Guadalupe River.prj: Guadalupe River Base Level Engineering

--- Guadalupe River.g01 (geometry) --- (continued)

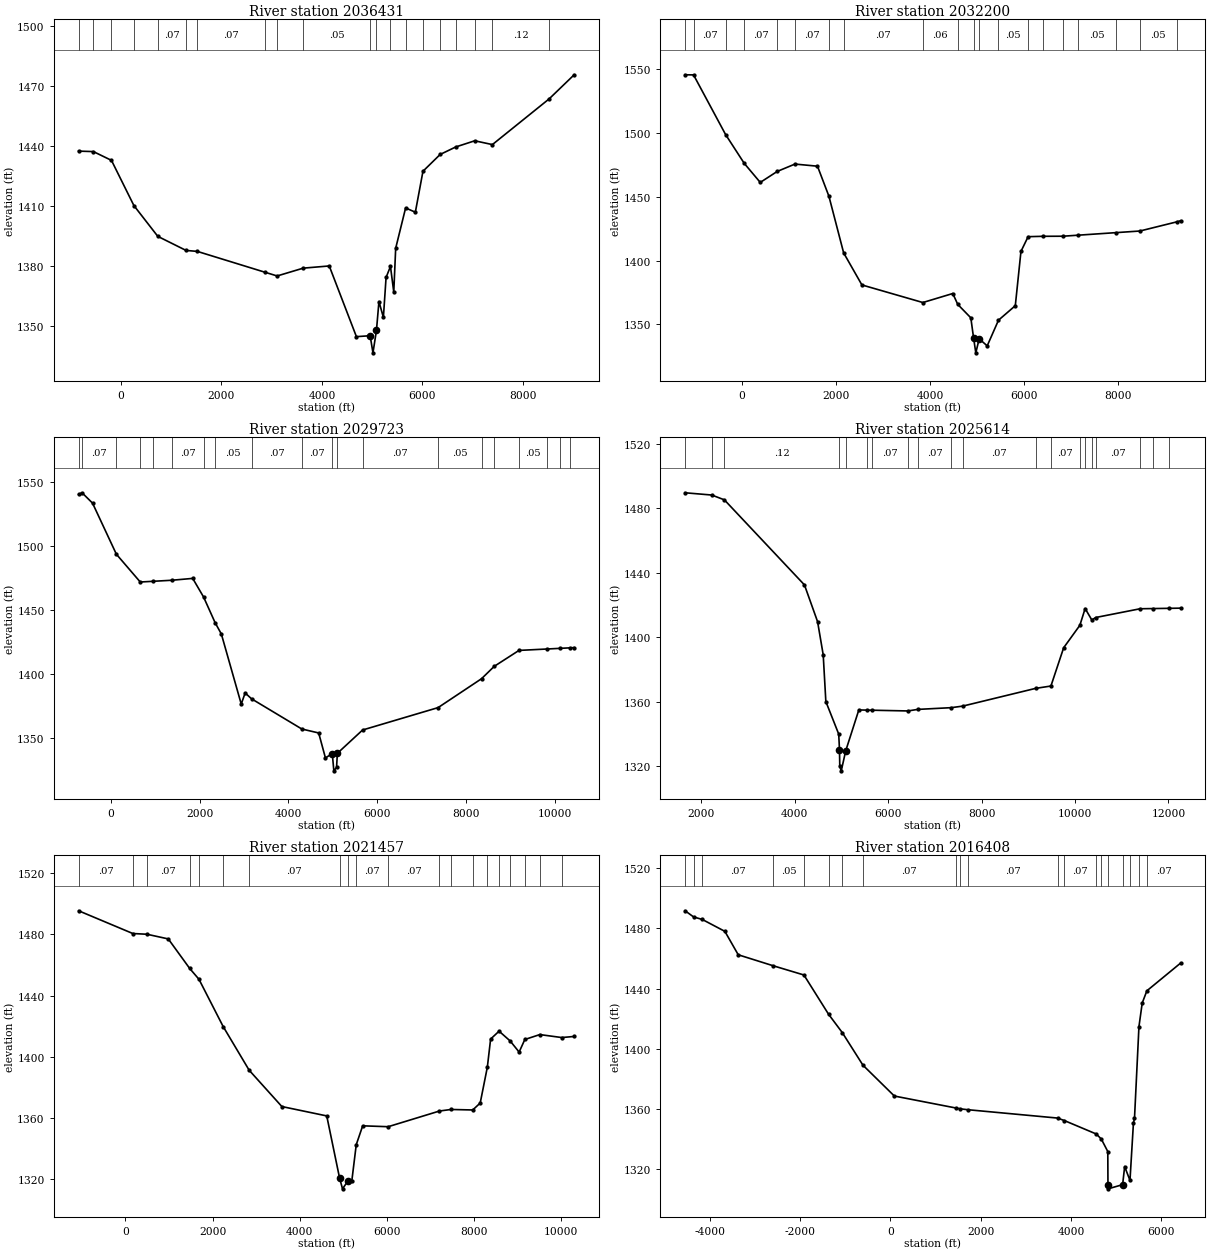
Type RM Length L Ch R = 1 ,2036431 ,4231,4231,4231
BEGIN DESCRIPTION:
Guadalupe River - 119
END DESCRIPTION:
XS GIS Cut Line= 4
        2013044.     13903069.69      2015075.54     13899663.88
      2017734.45     13898229.86      2016629.51     13895572.04
#Sta/Elev= 30
  -844.1 1437.44    -550  1437.2  -190.5 1432.81     256 1410.19   732.1 1394.77
  1294.3 1387.73  1519.2 1387.24  2868.5 1376.79  3107.8 1374.95  3626.8 1378.86
  4145.1 1379.96  4685.9 1344.57  4959.2 1345.04  5015.3 1336.47  5084.9 1347.73
  5134.4 1362.15  5222.9 1354.22  5276.3 1374.19  5363.7 1379.73  5429.5  1366.9
  5467.6 1388.81  5665.3    1409  5859.1 1406.86  6010.8 1427.36  6352.7 1435.76
    6663 1439.52  7041.3 1442.61  7392.8 1440.71  8521.6 1463.56  9020.9 1475.65
#Mann= 20 ,-1 , 0
  -844.1     .12       0    -550     .07       0  -190.5     .05       0
     256     .05       0   732.1     .07       0  1294.3     .05       0
  1519.2     .07       0  2868.5     .07       0  3107.8     .07       0
  3626.8     .05       0  4959.2     .04       0  5084.9     .07       0
  5363.7     .07       0  5665.3     .05       0  6010.8     .07       0
  6352.7     .05       0    6663     .07       0  7041.3     .12       0
  7392.8     .12       0  8521.6     .07       0
Bank Sta=4959.2,5084.9
XS Rating Curve= 0 ,0
Exp/Cntr=0.3,0.1

Type RM Length L Ch R = 1 ,2032200 ,2477,2477,2477
BEGIN DESCRIPTION:
Guadalupe River - 118
END DESCRIPTION:
XS GIS Cut Line= 5
      2013611.65     13907162.61       2015852.3     13905549.35
      2016778.44      13902800.8      2018092.96     13901187.53
      2017794.25     13898409.54
#Sta/Elev= 30
 -1210.1  1545.4 -1030.3  1545.3  -348.9 1498.61    47.9 1476.04   387.9 1461.15
     749 1469.75  1125.7 1475.51  1604.7 1473.85  1848.1  1450.3  2161.2 1405.98
  2549.3  1380.9  3845.2 1367.14  4481.8  1374.2  4587.3 1365.67  4865.2 1355.16
  4922.7 1339.72    4971 1327.76  5042.6 1338.75  5213.5 1333.22  5453.5 1353.32
    5811 1364.67  5930.9 1407.12  6083.2 1418.68  6407.8 1418.98    6823 1419.04
    7153 1419.86  7949.9 1421.84  8459.8 1423.11  9240.4 1430.24  9326.3 1431.12
#Mann= 20 ,-1 , 0
 -1210.1     .05       0 -1030.3     .07       0  -348.9     .05       0
    47.9     .07       0     749     .05       0  1125.7     .07       0
  1848.1     .05       0  2161.2     .07       0  3845.2     .06       0
  4587.3     .07       0  4922.7     .04       0  5042.6     .12       0
  5453.5     .05       0  6083.2     .07       0  6407.8     .05       0
    6823     .05       0    7153     .05       0  7949.9     .05       0
  8459.8     .05       0  9240.4     .07       0
Bank Sta=4922.7,5042.6
XS Rating Curve= 0 ,0
Exp/Cntr=0.3,0.1

Type RM Length L Ch R = 1 ,2029723 ,4109,4109,4109
BEGIN DESCRIPTION:
Guadalupe River - 117
END DESCRIPTION:
XS GIS Cut Line= 3
      2013731.11     13907192.51      2019287.97     13903637.32
      2018033.19     13899245.59
#Sta/Elev= 30
  -727.1 1540.19  -649.9 1541.49  -413.8 1533.41   123.4 1493.53   661.3 1471.85
   943.2 1472.39  1371.6 1473.22    1843 1474.67  2088.1 1460.13  2347.8 1440.11
  2488.2 1431.28  2936.4 1376.59  3024.4 1385.26  3169.6 1380.67  4301.7 1357.12
  4681.1 1354.04  4833.4 1334.54  4987.2 1337.99  5022.9 1324.48    5084 1327.18
  5102.2 1338.15  5670.3 1356.35  7371.2 1373.82  8349.7 1396.37  8636.8 1406.04
  9194.2 1418.47  9834.7 1419.58   10111 1420.06 10348.5 1420.48 10437.2 1420.63
#Mann= 20 ,-1 , 0
  -727.1     .05       0  -649.9     .07       0   123.4     .05       0
   661.3     .07       0   943.2     .07       0  1371.6     .07       0
  2088.1     .07       0  2347.8     .05       0  3169.6     .07       0
  4301.7     .07       0  4987.2     .04       0  5102.2     .05       0
  5670.3     .07       0  7371.2     .05       0  8349.7     .12       0
  8636.8     .07       0  9194.2     .05       0  9834.7     .07       0
   10111     .05       0 10348.5     .07       0
Bank Sta=4987.2,5102.2
XS Rating Curve= 0 ,0
Exp/Cntr=0.3,0.1

Type RM Length L Ch R = 1 ,2025614 ,4157,4157,4157
BEGIN DESCRIPTION:
Guadalupe River - 116
END DESCRIPTION:
XS GIS Cut Line= 3
      2022843.17     13908775.92      2018690.47     13900829.02
      2018152.69     13899275.46
#Sta/Elev= 30
  1651.3 1489.54  2222.9 1488.14  2492.3 1485.15    4207 1432.36  4488.3 1409.52
  4608.5 1388.99    4665 1359.98  4940.7 1339.76  4957.2 1329.95  4963.5 1319.77
  4994.9 1316.97  5089.6  1329.3    5371 1354.76  5541.5 1354.66  5663.9 1354.59
  6423.3 1354.14  6631.4  1355.1  7351.9 1356.18  7595.7 1357.14  9155.1 1368.14
  9484.3 1369.61  9757.2 1393.37 10104.1  1407.3 10216.9 1417.71 10359.9  1410.6
 10442.6 1412.13 11394.3 1417.56 11671.7 1417.68 12014.2 1417.83 12261.8 1417.94
#Mann= 20 ,-1 , 0
  1651.3     .12       0  2222.9     .07       0  2492.3     .12       0
  4957.2     .04       0  5089.6     .12       0  5541.5     .06       0
  5663.9     .07       0  6423.3     .05       0  6631.4     .07       0
  7351.9     .05       0  7595.7     .07       0  9155.1     .05       0
  9484.3     .07       0 10104.1     .12       0 10216.9     .07       0
 10359.9     .12       0 10442.6     .07       0 11394.3     .05       0
 11671.7     .07       0 12014.2     .05       0
Bank Sta=4957.2,5089.6
XS Rating Curve= 0 ,0
Exp/Cntr=0.3,0.1

Type RM Length L Ch R = 1 ,2021457 ,5049,5049,5049
BEGIN DESCRIPTION:
Guadalupe River - 115
END DESCRIPTION:
XS GIS Cut Line= 5
      2024725.29     13907371.72      2023590.04     13905429.84
      2023231.53     13903039.81      2019556.85     13901934.42
      2018331.97     13899335.26
#Sta/Elev= 30
 -1073.5 1495.39   170.8 1480.53   494.7 1480.06   984.6 1477.01  1475.6 1457.74
  1689.1 1450.64  2244.1 1419.79  2841.4 1391.24  3592.5  1367.5  4622.8 1361.38
  4915.8 1321.01  4984.8 1313.74  5113.7 1319.07  5197.2 1318.63  5300.3  1342.6
  5447.8 1354.91  6032.7 1354.33  7211.4 1364.58  7475.2 1365.59  7974.4 1365.26
  8146.1 1369.81  8309.9 1393.25    8385 1411.58  8578.9 1416.74  8833.4 1410.36
  9039.5 1403.09  9170.5 1411.31    9515 1414.51   10018 1412.58 10303.3 1413.29
#Mann= 20 ,-1 , 0
 -1073.5     .07       0   170.8     .05       0   494.7     .07       0
  1475.6     .12       0  1689.1     .07       0  2244.1     .05       0
  2841.4     .07       0  4915.8     .04       0  5113.7     .05       0
  5300.3     .07       0  6032.7     .07       0  7211.4     .07       0
  7475.2     .05       0  7974.4     .12       0  8309.9     .07       0
  8578.9     .05       0  8833.4     .12       0  9170.5     .07       0
    9515     .07       0   10018     .05       0
Bank Sta=4915.8,5113.7
XS Rating Curve= 0 ,0
Exp/Cntr=0.3,0.1

Type RM Length L Ch R = 1 ,2016408 ,2726,2726,2726
BEGIN DESCRIPTION:
Guadalupe River - 114.8
END DESCRIPTION:
XS GIS Cut Line= 6
      2025040.53      13907235.7      2023998.86     13905347.66
      2023556.15     13902912.77      2022853.02     13900529.96
      2021448.53     13898552.14      2020274.93     13897743.52
#Sta/Elev= 30
 -4541.3  1491.8 -4352.7 1487.69 -4160.6 1486.01 -3661.1 1478.09 -3365.1 1462.48
 -2591.2 1455.16 -1911.8 1449.02 -1367.2 1422.91 -1061.2 1410.57  -605.1 1388.91
    89.8 1368.37  1444.6 1360.44  1548.1 1359.83  1725.9 1359.23  3702.7 1353.69
  3854.5    1352    4559 1343.07  4669.7 1339.71  4813.1 1331.39  4816.9 1309.34
  4819.2 1306.54  5141.3 1309.34  5186.4  1321.4    5304 1312.14  5380.7 1350.42
  5404.1 1353.49  5502.6 1414.62    5575 1430.35    5678 1438.48  6425.2 1456.97
#Mann= 20 ,-1 , 0
 -4541.3     .07       0 -4352.7     .07       0 -4160.6     .07       0
 -2591.2     .05       0 -1911.8     .12       0 -1367.2     .05       0
 -1061.2     .07       0  -605.1     .07       0  1444.6     .07       0
  1548.1     .05       0  1725.9     .07       0  3702.7     .05       0
  3854.5     .07       0    4559     .07       0  4669.7     .05       0
  4816.9     .05       0  5141.3     .12       0    5304     .12       0
  5502.6     .07       0    5678     .07       0
Bank Sta=4816.9,5141.3
XS Rating Curve= 0 ,0
Exp/Cntr=0.3,0.1

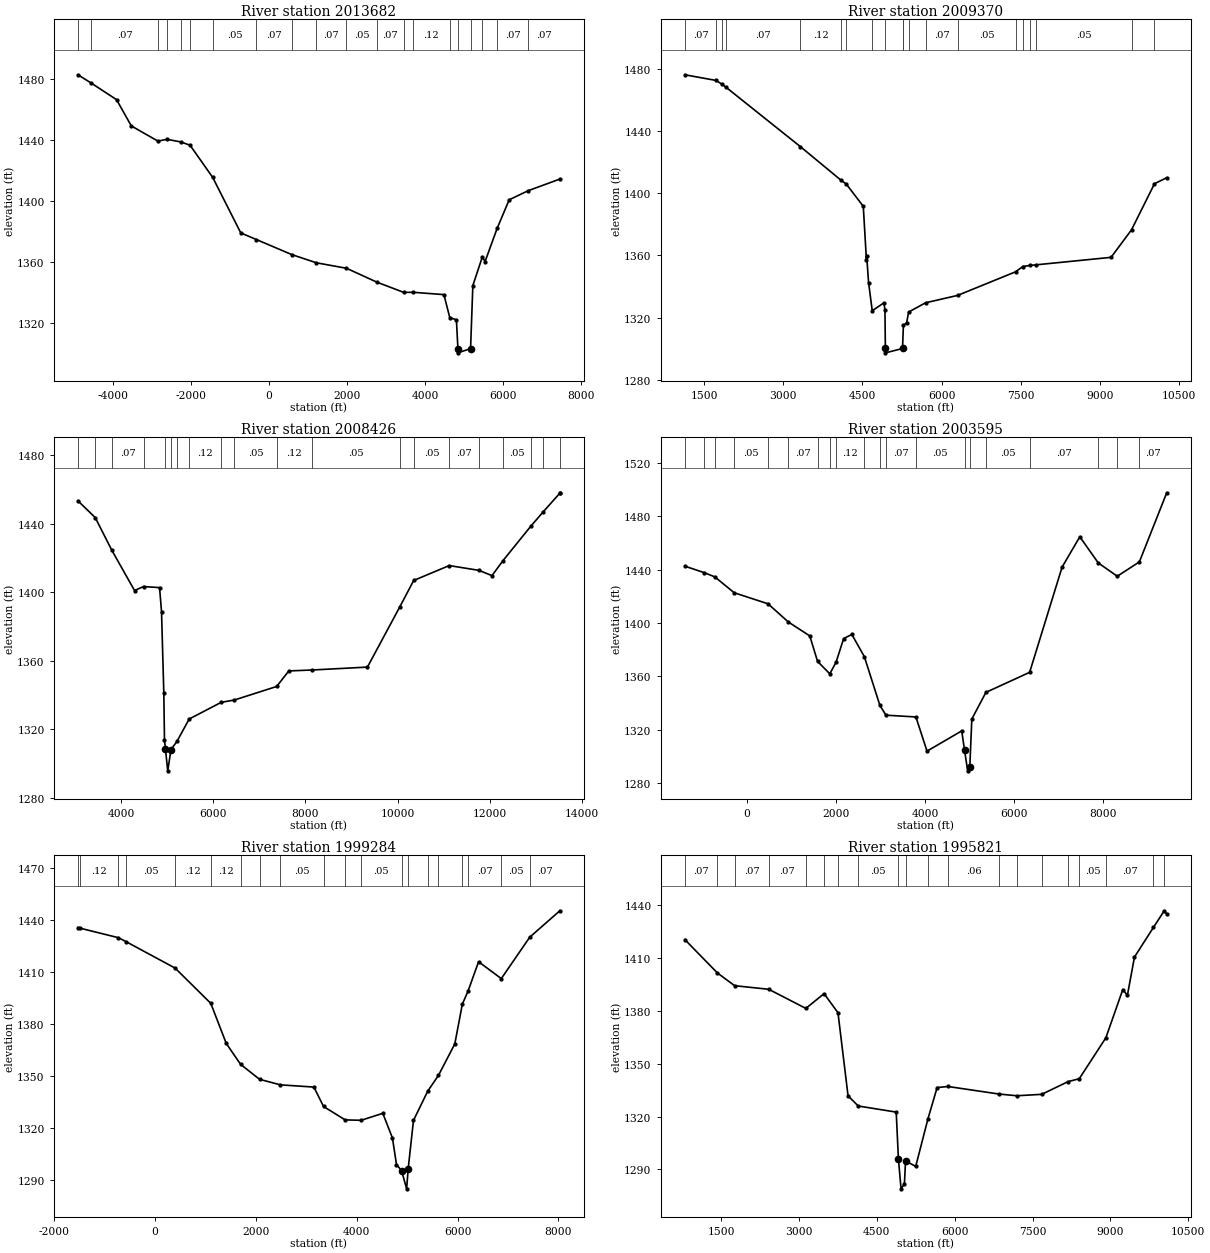
Type RM Length L Ch R = 1 ,2013682 ,4312,4312,4312
BEGIN DESCRIPTION:
Guadalupe River - 114.6
END DESCRIPTION:
XS GIS Cut Line= 5
      2025248.84     13907092.42      2024233.23     13905204.44
      2023347.82     13899162.77      2023504.07     13897222.66
      2022644.69     13895243.49
#Sta/Elev= 30
 -4896.2 1482.99 -4550.5 1477.45 -3906.1 1466.64 -3528.7 1449.42 -2846.5 1439.43
   -2614 1440.61 -2258.8 1438.89   -2023 1436.75 -1442.3 1415.62  -721.5 1379.14
    -322  1374.8   587.1 1364.91  1214.1 1359.54  1988.2 1355.93  2757.7 1346.92
  3455.3  1340.1  3694.7 1340.16  4485.2 1338.64  4636.6 1323.52  4806.3  1322.1
  4844.5  1303.2  4846.9  1300.4  5169.3  1303.2  5227.6 1344.59  5473.2 1363.51
  5539.7 1360.26  5850.4 1382.12  6158.8  1400.9  6649.8 1406.91  7457.9 1414.51
#Mann= 20 ,-1 , 0
 -4896.2     .07       0 -4550.5     .07       0 -2846.5     .12       0
   -2614     .07       0 -2258.8     .12       0   -2023     .07       0
 -1442.3     .05       0    -322     .07       0   587.1     .05       0
  1214.1     .07       0  1988.2     .05       0  2757.7     .07       0
  3455.3     .07       0  3694.7     .12       0  4636.6     .07       0
  4844.5     .05       0  5169.3     .07       0  5473.2     .05       0
  5850.4     .07       0  6649.8     .07       0
Bank Sta=4844.5,5169.3
XS Rating Curve= 0 ,0
Exp/Cntr=0.3,0.1

Type RM Length L Ch R = 1 ,2009370 ,944,944,944
BEGIN DESCRIPTION:
Guadalupe River - 114.3
END DESCRIPTION:
XS GIS Cut Line= 4
      2028139.45     13903095.03      2026303.54     13901350.27
      2026394.69     13899566.41      2023150.98     13896019.77
#Sta/Elev= 30
  1136.7 1476.14  1729.6 1472.49  1836.5 1470.13  1916.4 1468.12  3324.2 1429.95
  4095.5 1408.28  4193.9 1405.87  4515.8 1391.55  4575.3  1357.1  4580.4 1359.62
  4615.9 1342.51  4685.5  1324.4  4906.3 1329.47  4926.3 1324.86  4933.9 1300.12
  4936.3 1297.32  5259.2 1300.12  5275.6 1315.06  5336.9 1316.61  5373.9 1323.53
  5695.2 1329.51  6302.1 1334.26  7399.8 1349.43    7537 1352.83  7674.2 1353.55
  7782.6  1353.9  9207.9 1358.73  9595.3 1376.45 10030.1 1406.09 10261.9 1409.94
#Mann= 20 ,-1 , 0
  1136.7     .07       0  1729.6     .12       0  1836.5     .12       0
  1916.4     .07       0  3324.2     .12       0  4095.5     .05       0
  4193.9     .12       0  4685.5     .05       0  4933.9     .05       0
  5259.2     .05       0  5275.6     .05       0  5373.9     .12       0
  5695.2     .07       0  6302.1     .05       0  7399.8     .12       0
    7537     .07       0  7674.2     .07       0  7782.6     .05       0
  9595.3     .07       0 10030.1     .05       0
Bank Sta=4933.9,5259.2
XS Rating Curve= 0 ,0
Exp/Cntr=0.3,0.1

Type RM Length L Ch R = 1 ,2008426 ,4831,4831,4831
BEGIN DESCRIPTION:
Guadalupe River - 114
END DESCRIPTION:
XS GIS Cut Line= 5
      2028173.33     13901330.58      2027374.74     13899941.73
      2023590.02     13896365.34      2022756.68     13895115.34
      2022479.08     13892998.63
#Sta/Elev= 30
  3068.1 1453.27  3442.1 1443.52  3804.1 1424.34    4295  1400.9  4489.8 1403.24
  4837.3 1402.61  4879.8 1388.63  4929.6 1340.91  4943.7 1313.64  4964.8 1308.33
  5014.7 1295.64  5084.9 1308.01  5214.3 1312.84  5479.2 1325.89  6174.8 1335.65
  6453.7 1336.95  7375.7 1344.89  7638.8 1353.97  8133.1  1354.5  9343.6 1356.21
 10047.6 1391.49 10346.4 1406.79 11116.3 1415.48 11760.6 1412.69 12043.4 1409.61
 12283.5 1418.41 12881.2 1438.34 13151.2 1446.77 13512.3 1457.68 13514.5 1457.98
#Mann= 20 ,-1 , 0
  3068.1     .07       0  3442.1     .05       0  3804.1     .07       0
  4489.8     .12       0  4964.8     .04       0  5084.9     .07       0
  5214.3     .07       0  5479.2     .12       0  6174.8     .12       0
  6453.7     .05       0  7375.7     .12       0  8133.1     .05       0
 10047.6     .07       0 10346.4     .05       0 11116.3     .07       0
 11760.6     .07       0 12283.5     .05       0 12881.2     .07       0
 13151.2     .07       0 13512.3     .05       0
Bank Sta=4964.8,5084.9
XS Rating Curve= 0 ,0
Exp/Cntr=0.3,0.1

Type RM Length L Ch R = 1 ,2003595 ,4311,4311,4311
BEGIN DESCRIPTION:
Guadalupe River - 113
END DESCRIPTION:
XS GIS Cut Line= 4
      2028867.79     13900879.26      2029041.41     13897719.51
      2024874.74     13894177.84      2025083.07     13891990.36
#Sta/Elev= 30
 -1396.7 1442.63    -958 1437.72    -723 1434.59  -286.5 1422.67   473.1 1414.42
   927.7 1400.84  1411.8 1390.32  1586.4 1371.24  1861.7 1361.93  2003.3 1370.73
  2172.5 1388.38    2357 1391.43  2637.4 1374.84  2987.7 1338.23  3124.4 1330.94
  3796.8 1329.61  4046.2 1303.98    4826 1319.16  4889.7 1304.72    4960 1289.23
  5007.7 1292.03  5053.3 1328.05  5369.6 1348.02  6352.5 1363.06  7081.8 1441.91
  7480.3 1464.63  7894.7 1445.08  8321.6 1435.07  8818.9 1445.82  9433.7 1497.62
#Mann= 20 ,-1 , 0
 -1396.7     .07       0    -958     .12       0    -723     .07       0
  -286.5     .05       0   473.1     .12       0   927.7     .07       0
  1586.4     .05       0  1861.7     .12       0  2003.3     .12       0
  2637.4     .05       0  2987.7     .07       0  3124.4     .07       0
  3796.8     .05       0  4889.7     .04       0  5007.7     .05       0
  5369.6     .05       0  6352.5     .07       0  7894.7     .12       0
  8321.6     .07       0  8818.9     .07       0
Bank Sta=4889.7,5007.7
XS Rating Curve= 0 ,0
Exp/Cntr=0.3,0.1

Type RM Length L Ch R = 1 ,1999284 ,3463,3463,3463
BEGIN DESCRIPTION:
Guadalupe River - 112
END DESCRIPTION:
XS GIS Cut Line= 3
      2029076.13      13900670.9      2029840.02     13893275.06
      2029423.34      13891191.7
#Sta/Elev= 30
 -1530.8 1435.79   -1485 1435.37  -729.1  1429.9  -578.7 1427.64   396.1 1412.33
  1104.4 1391.93  1410.7 1368.77  1695.6 1356.66  2071.9    1348  2484.6 1344.79
  3149.9 1343.51  3340.8 1332.29  3770.3 1324.53  4087.2  1324.3  4517.1 1328.34
  4708.1 1314.04  4788.5 1298.67  4889.1 1295.21  4989.9 1284.66  5019.8 1296.13
  5125.4 1324.22  5408.3 1341.16  5620.6 1350.25  5945.2 1368.46  6094.8 1391.46
  6209.1 1399.09  6416.9 1415.99  6867.5 1406.24  7431.9 1430.19    8029 1445.46
#Mann= 20 ,-1 , 0
 -1530.8     .07       0   -1485     .12       0  -729.1     .07       0
  -578.7     .05       0   396.1     .12       0  1104.4     .12       0
  1695.6     .07       0  2071.9     .12       0  2484.6     .05       0
  3340.8     .07       0  3770.3     .05       0  4087.2     .05       0
  4889.1     .04       0  5019.8     .05       0  5408.3     .05       0
  5620.6     .05       0  6094.8     .12       0  6209.1     .07       0
  6867.5     .05       0  7431.9     .07       0
Bank Sta=4889.1,5019.8
XS Rating Curve= 0 ,0
Exp/Cntr=0.3,0.1

Type RM Length L Ch R = 1 ,1995821 ,4600,4600,4600
BEGIN DESCRIPTION:
Guadalupe River - 111
END DESCRIPTION:
XS GIS Cut Line= 3
       2031228.9     13899733.43      2031610.85     13897268.12
      2035256.33     13891539.51
#Sta/Elev= 30
   800.9 1420.63  1428.6 1401.65  1760.7 1394.41  2417.2 1392.38  3132.5 1381.51
  3483.9  1389.9  3751.8 1379.03  3945.6 1331.83  4141.9 1326.04  4873.6 1322.57
  4915.9 1296.14  4966.7 1278.96  5031.7 1281.76  5053.6 1294.79  5249.5 1291.73
  5485.5 1318.79  5661.8 1336.51    5869 1337.13  6857.5 1332.82  7200.5 1331.86
  7677.2 1332.67  8185.7  1339.9  8400.9 1341.54  8913.6 1364.84  9239.7 1392.25
  9327.8  1388.9  9464.1 1410.69  9830.2 1427.55 10037.1 1436.99 10085.8 1435.18
#Mann= 20 ,-1 , 0
   800.9     .07       0  1428.6     .12       0  1760.7     .07       0
  2417.2     .07       0  3132.5     .07       0  3483.9     .05       0
  3751.8     .07       0  4141.9     .05       0  4915.9     .04       0
  5053.6     .12       0  5485.5     .12       0    5869     .06       0
  6857.5     .07       0  7200.5     .05       0  7677.2     .06       0
  8185.7     .07       0  8400.9     .05       0  8913.6     .07       0
  9830.2     .07       0 10037.1     .05       0
Bank Sta=4915.9,5053.6
XS Rating Curve= 0 ,0
Exp/Cntr=0.3,0.1

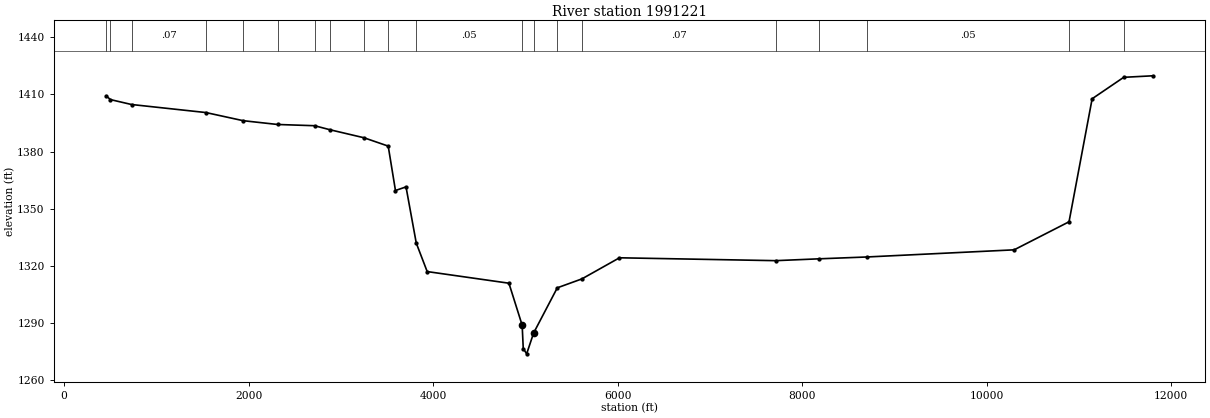
Type RM Length L Ch R = 1 ,1991221 ,3704,3704,3704
BEGIN DESCRIPTION:
Guadalupe River - 110
END DESCRIPTION:
XS GIS Cut Line= 4
      2032305.25     13899941.74      2035638.63     13898969.51
      2037409.46     13895288.95      2036055.83     13891748.68
#Sta/Elev= 30
   456.6 1409.27   502.8 1407.32   731.2 1404.74    1538 1400.51  1941.1 1396.24
  2314.2 1394.25  2714.8  1393.6    2885 1391.45  3251.3 1387.27  3513.3 1382.89
  3591.8 1359.57  3706.3 1361.47  3817.5 1331.93  3935.7 1316.99  4821.6 1310.88
  4965.2 1288.81    4977 1276.58  5013.9 1273.78  5089.4 1284.73  5345.9 1308.46
  5612.5 1313.14  6020.1 1324.23  7712.1 1322.72  8183.4 1323.69  8699.2 1324.65
 10297.9 1328.41 10892.6 1343.14 11143.1 1407.76 11485.2 1419.02 11803.5 1419.83
#Mann= 20 ,-1 , 0
   456.6     .05       0   502.8     .12       0   731.2     .07       0
    1538     .07       0  1941.1     .05       0  2314.2     .07       0
  2714.8     .12       0    2885     .05       0  3251.3     .05       0
  3513.3     .07       0  3817.5     .05       0  4965.2     .04       0
  5089.4     .05       0  5345.9     .05       0  5612.5     .07       0
  7712.1     .12       0  8183.4     .07       0  8699.2     .05       0
 10892.6     .12       0 11485.2     .07       0
Bank Sta=4965.2,5089.4
XS Rating Curve= 0 ,0
Exp/Cntr=0.3,0.1