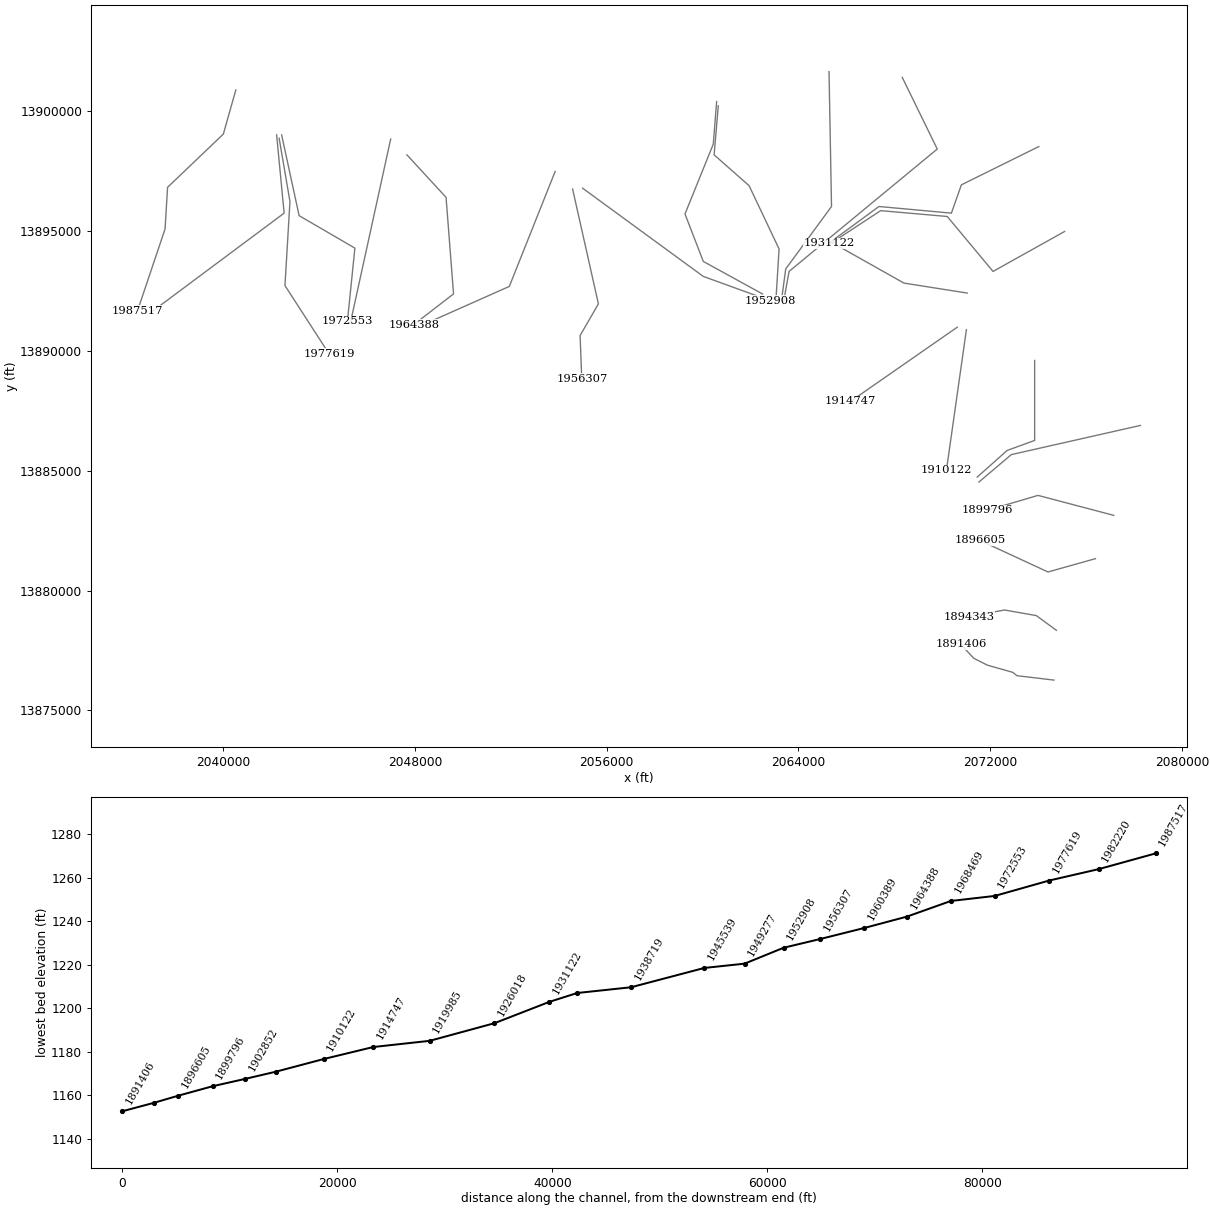
HEC-RAS study Guadalupe River.prj: Guadalupe River Base Level Engineering

--- Guadalupe River.g01 (geometry) --- (continued)

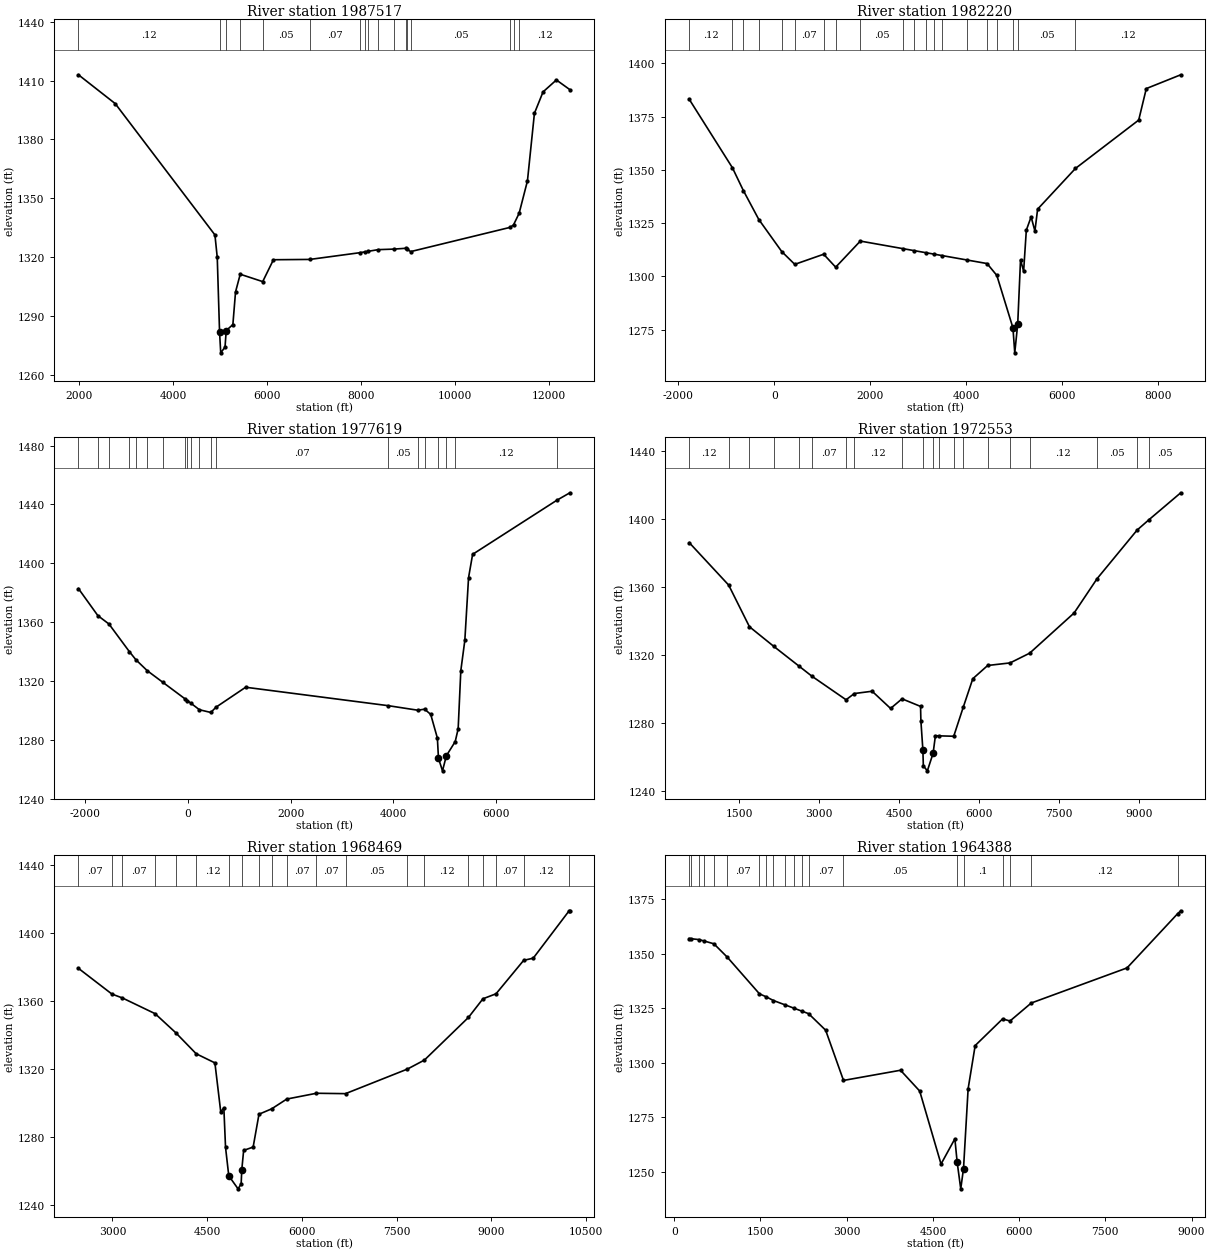
Type RM Length L Ch R = 1 ,1987517 ,5297,5297,5297
BEGIN DESCRIPTION:
Guadalupe River - 109
END DESCRIPTION:
XS GIS Cut Line= 5
      2040534.45     13900879.21      2040013.63     13899038.95
      2037687.24     13896816.73      2037583.07     13895080.62
      2036437.62     13891678.96
#Sta/Elev= 30
  1979.7 1412.93  2762.8 1398.24  4884.4 1331.36  4933.8 1319.89  4983.1 1281.79
  5007.7  1271.3  5099.2  1274.2  5124.7 1282.65  5266.2  1285.7  5322.8 1302.31
  5422.8 1311.34  5900.9 1307.58  6129.2 1318.72  6904.5 1318.88  7962.7 1322.29
  8069.5 1322.71  8140.7 1322.99  8357.6 1323.86  8695.3 1324.14  8957.8 1324.58
  8978.3 1324.11  9048.9 1322.86 11166.1 1335.21 11238.1 1336.46   11358 1342.41
 11534.7  1358.9 11683.1 1393.31 11866.8 1404.21 12150.3 1410.29   12438 1405.34
#Mann= 17 ,-1 , 0
  1979.7     .12       0  4983.1     .04       0  5124.7     .07       0
  5422.8     .06       0  5900.9     .05       0  6904.5     .07       0
  7962.7     .05       0  8069.5     .07       0  8140.7     .05       0
  8357.6     .12       0  8695.3     .07       0  8957.8     .12       0
  8978.3     .07       0  9048.9     .05       0 11166.1     .12       0
 11238.1     .05       0   11358     .12       0
Bank Sta=4983.1,5124.7
XS Rating Curve= 0 ,0
Exp/Cntr=0.3,0.1

Type RM Length L Ch R = 1 ,1982220 ,4601,4601,4601
BEGIN DESCRIPTION:
Guadalupe River - 108
END DESCRIPTION:
XS GIS Cut Line= 3
      2042235.85     13899004.22      2042548.35     13895740.34
        2036959.     13891574.36
#Sta/Elev= 30
 -1771.8 1383.09  -871.6 1350.95  -644.3 1340.28  -320.8 1326.64   157.7 1311.59
   428.5 1305.61  1030.6 1310.36  1281.5 1304.28  1795.4 1316.54  2688.2 1312.97
  2907.1  1312.1  3168.8 1311.06  3334.2  1310.4  3496.4 1309.75    4022 1307.65
  4438.7 1305.99  4642.3 1300.42  4978.4 1275.79  5016.3 1264.06  5078.2 1277.69
  5136.5 1307.72  5201.2  1302.4  5257.5 1321.66  5357.5  1327.9  5436.8 1321.26
  5493.1 1331.53  6282.2 1350.65  7601.2 1373.36  7759.7 1388.15  8478.1 1394.63
#Mann= 20 ,-1 , 0
 -1771.8     .12       0  -871.6     .12       0  -644.3     .05       0
  -320.8     .05       0   157.7     .05       0   428.5     .07       0
  1030.6     .05       0  1281.5     .07       0  1795.4     .05       0
  2688.2     .05       0  2907.1     .07       0  3168.8     .05       0
  3334.2     .07       0  3496.4     .05       0    4022     .07       0
  4438.7     .05       0  4642.3     .05       0  4978.4     .04       0
  5078.2     .05       0  6282.2     .12       0
Bank Sta=4978.4,5078.2
XS Rating Curve= 0 ,0
Exp/Cntr=0.3,0.1

Type RM Length L Ch R = 1 ,1977619 ,5066,5066,5066
BEGIN DESCRIPTION:
Guadalupe River - 107
END DESCRIPTION:
XS GIS Cut Line= 4
      2042340.01     13898865.36      2042791.41     13896226.45
      2042583.07     13892719.51      2044423.33     13889872.32
#Sta/Elev= 30
 -2136.5 1382.74 -1757.8 1364.36   -1541 1358.64 -1143.9 1339.89   -1015  1334.3
  -794.4  1326.9  -492.8 1319.06   -51.9 1307.59   -14.8 1306.62    54.2 1304.83
   222.3 1300.36   444.4 1298.51   543.7 1302.05  1123.2 1315.66  3906.1 1303.11
  4478.3 1300.04  4611.8 1300.74  4730.9 1297.19  4860.9 1281.06    4882 1267.34
  4960.6 1258.82  5035.6 1269.06  5208.4 1278.72  5265.9 1287.42  5317.4 1326.91
  5395.9 1347.54  5468.5 1390.19  5547.6 1406.02    7189 1442.79    7444 1447.88
#Mann= 20 ,-1 , 0
 -2136.5     .12       0 -1757.8     .07       0   -1541     .12       0
 -1143.9     .05       0   -1015     .07       0  -794.4     .05       0
  -492.8     .07       0   -51.9     .05       0   -14.8     .07       0
    54.2     .05       0   222.3     .07       0   444.4     .12       0
   543.7     .07       0  3906.1     .05       0  4478.3     .07       0
  4611.8     .05       0    4882     .04       0  5035.6     .12       0
  5208.4     .12       0    7189     .07       0
Bank Sta=4882,5035.6
XS Rating Curve= 0 ,0
Exp/Cntr=0.3,0.1

Type RM Length L Ch R = 1 ,1972553 ,4084,4084,4084
BEGIN DESCRIPTION:
Guadalupe River - 106
END DESCRIPTION:
XS GIS Cut Line= 4
      2042444.18     13899004.26      2043173.35     13895636.17
      2045499.74     13894282.01      2045187.42     13891228.26
#Sta/Elev= 30
   567.8 1385.85  1305.5 1360.93  1695.2 1336.43  2153.6 1324.83  2631.7 1313.09
  2865.5 1307.35  3504.9 1293.51  3660.3 1297.17  3993.8 1298.52  4339.1  1288.4
  4553.8 1294.06  4900.9  1289.6  4906.8 1281.25  4943.9 1264.18  4953.1 1254.65
  5028.1 1251.73  5135.9 1262.06  5178.9 1272.36  5237.5 1272.31  5522.2 1272.06
  5702.1 1289.27  5879.7 1305.88  6158.3 1313.66  6577.8 1315.17  6944.6 1320.89
  7778.3 1344.55    8208 1364.69  8958.6 1393.28  9176.9 1399.26  9775.4 1415.18
#Mann= 20 ,-1 , 0
   567.8     .12       0  1305.5     .12       0  1695.2     .07       0
  2153.6     .07       0  2631.7     .05       0  2865.5     .07       0
  3504.9     .07       0  3660.3     .12       0  4553.8     .05       0
  4943.9     .04       0  5135.9     .07       0  5237.5     .05       0
  5522.2     .07       0  5702.1     .12       0  6158.3     .07       0
  6577.8     .05       0  6944.6     .12       0    8208     .05       0
  8958.6     .12       0  9176.9     .05       0
Bank Sta=4943.9,5135.9
XS Rating Curve= 0 ,0
Exp/Cntr=0.3,0.1

Type RM Length L Ch R = 1 ,1968469 ,4081,4081,4081
BEGIN DESCRIPTION:
Guadalupe River - 105
END DESCRIPTION:
XS GIS Cut Line= 2
      2046992.79      13898830.6      2045326.52     13891228.26
#Sta/Elev= 30
  2460.5 1379.19  2990.5 1364.05  3157.6 1361.74  3674.8  1352.5  3999.4 1341.37
    4325 1328.92  4621.7 1323.54  4714.4 1294.63  4763.4 1297.09  4790.1  1273.8
  4841.3 1257.09  4988.2 1249.41  5037.4 1252.31  5046.8 1260.41  5076.8 1272.03
  5227.3    1274  5319.7 1293.32  5520.3 1296.49    5760 1302.25    6230 1305.66
  6689.8 1305.43  7670.6  1319.9  7939.6  1325.2  8637.4 1350.32  8866.2 1361.26
  9073.7 1364.21  9511.5  1383.9  9662.3 1385.15 10231.4 1413.06 10243.3 1413.05
#Mann= 20 ,-1 , 0
  2460.5     .07       0  2990.5     .12       0  3157.6     .07       0
  3674.8     .12       0  3999.4     .07       0    4325     .12       0
  4841.3     .04       0  5046.8     .07       0  5319.7     .12       0
  5520.3     .05       0    5760     .07       0    6230     .07       0
  6689.8     .05       0  7670.6     .07       0  7939.6     .12       0
  8637.4     .07       0  8866.2     .05       0  9073.7     .07       0
  9511.5     .12       0 10231.4     .05       0
Bank Sta=4841.3,5046.8
XS Rating Curve= 0 ,0
Exp/Cntr=0.3,0.1

Type RM Length L Ch R = 1 ,1964388 ,3999,3999,3999
BEGIN DESCRIPTION:
Guadalupe River - 104
END DESCRIPTION:
XS GIS Cut Line= 4
      2047669.91     13898170.87      2049301.82     13896400.06
      2049614.32     13892372.28      2047950.44     13891089.71
#Sta/Elev= 30
   262.3 1356.97   295.7 1356.88   425.8 1356.51   515.4 1355.89   690.7 1354.56
   925.2 1348.38  1483.4 1331.61  1596.2 1330.31  1725.8 1328.56  1934.9  1326.5
  2085.5 1325.02  2224.5 1323.65  2337.8 1322.53  2633.9 1314.97  2944.9 1291.92
  3936.9 1296.59  4270.2 1287.06  4641.4 1253.58  4882.1 1265.16  4922.2 1254.38
  4984.3 1242.22  5032.5 1251.49  5112.8 1288.12  5235.2 1307.91  5712.6 1320.14
  5840.9 1319.16  6210.7 1327.41  7877.2 1343.51  8758.3  1368.4  8811.1  1369.7
#Mann= 20 ,-1 , 0
   262.3     .05       0   295.7     .07       0   425.8     .12       0
   515.4     .05       0   690.7     .07       0   925.2     .07       0
  1483.4     .05       0  1596.2     .07       0  1725.8     .07       0
  1934.9     .05       0  2085.5     .07       0  2224.5     .12       0
  2337.8     .07       0  2944.9     .05       0  4922.2     .04       0
  5032.5      .1       0  5712.6     .05       0  5840.9     .07       0
  6210.7     .12       0  8758.3     .07       0
Bank Sta=4922.2,5032.5
XS Rating Curve= 0 ,0
Exp/Cntr=0.3,0.1

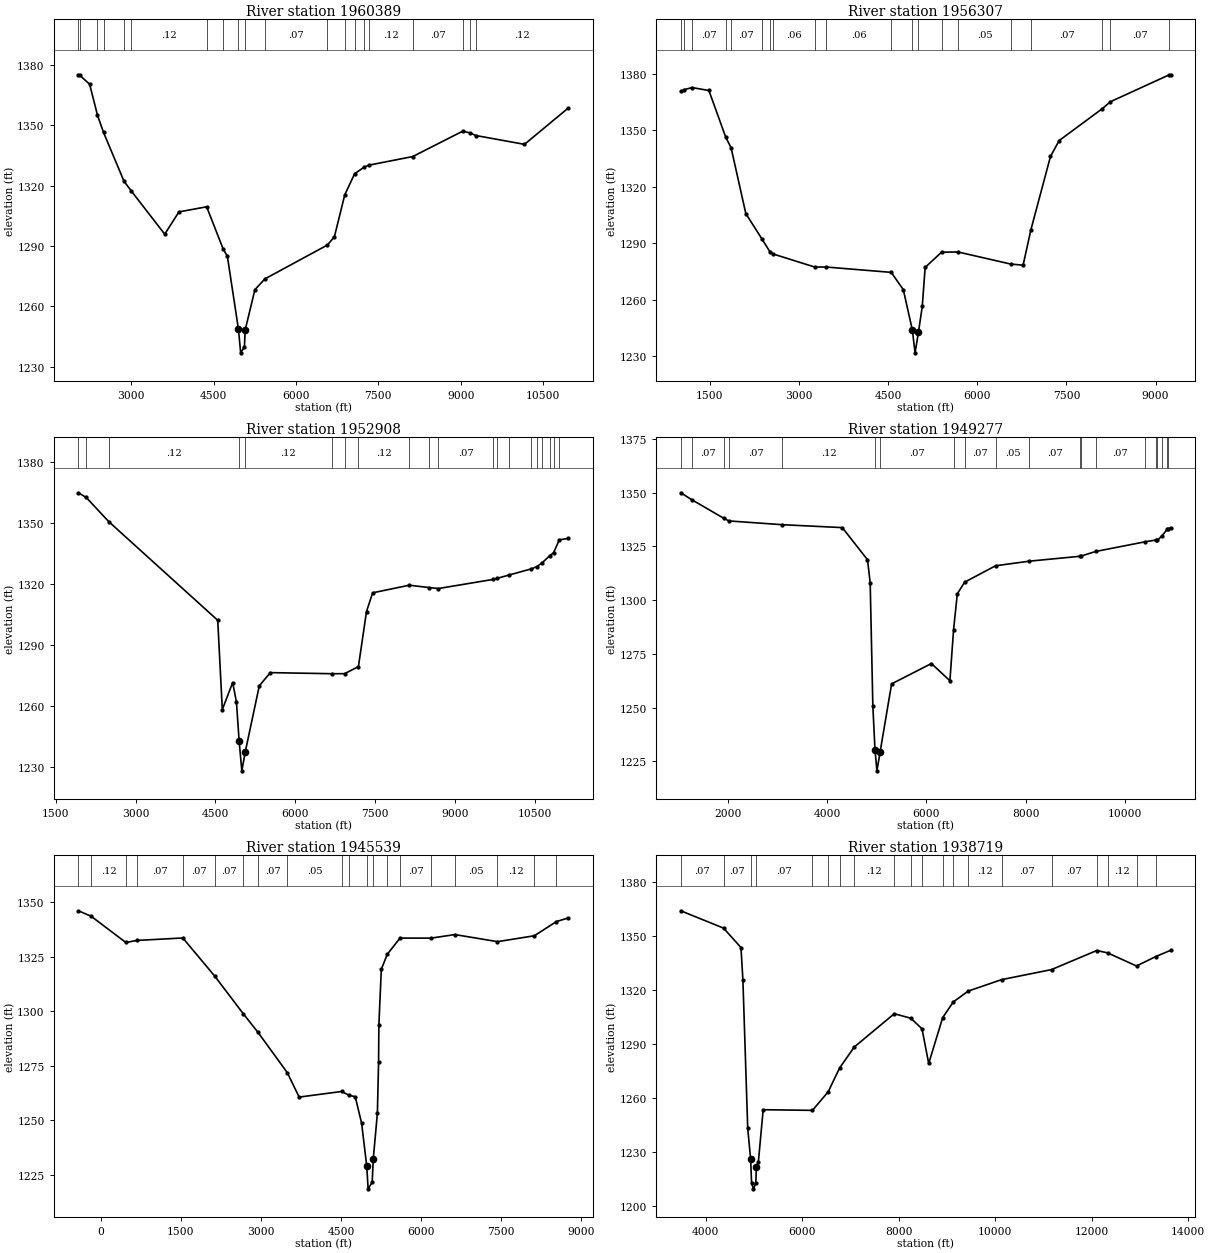
Type RM Length L Ch R = 1 ,1960389 ,4082,4082,4082
BEGIN DESCRIPTION:
Guadalupe River - 103
END DESCRIPTION:
XS GIS Cut Line= 3
      2053850.44     13897476.46      2051940.71     13892684.78
      2048503.24     13891157.02
#Sta/Elev= 30
  2038.5 1375.18  2067.9 1374.84  2244.6 1370.46  2386.9 1355.07  2496.9 1346.54
  2869.7 1322.27  3001.7 1317.45  3611.8 1295.93  3870.1 1307.01    4375 1309.55
  4675.6 1288.57  4752.8 1284.91  4954.4 1248.62  4994.4 1236.95  5063.5 1239.95
  5075.8 1248.22  5253.7 1268.35  5437.6 1273.74  6573.3 1290.54  6701.3 1294.63
    6890 1315.49    7070 1325.99  7248.5 1329.36  7339.4  1330.3  8129.3 1334.54
  9038.1 1347.15    9172 1346.28  9275.9 1344.99 10163.1  1340.6 10958.4 1358.61
#Mann= 20 ,-1 , 0
  2038.5     .05       0  2067.9     .12       0  2386.9     .07       0
  2496.9     .12       0  2869.7     .07       0  3001.7     .12       0
    4375     .05       0  4675.6     .12       0  4954.4     .04       0
  5075.8     .12       0  5437.6     .07       0  6573.3     .12       0
    6890     .12       0    7070     .05       0  7248.5     .05       0
  7339.4     .12       0  8129.3     .07       0  9038.1     .12       0
    9172     .07       0  9275.9     .12       0
Bank Sta=4954.4,5075.8
XS Rating Curve= 0 ,0
Exp/Cntr=0.3,0.1

Type RM Length L Ch R = 1 ,1956307 ,3399,3399,3399
BEGIN DESCRIPTION:
Guadalupe River - 102
END DESCRIPTION:
XS GIS Cut Line= 4
      2054579.59     13896747.33      2055655.99     13891955.62
       2054892.1     13890636.17      2054961.54     13888830.65
#Sta/Elev= 30
  1009.5 1370.66  1070.3 1371.62  1200.7 1372.68  1483.4 1371.14    1767 1346.33
  1856.6 1340.77  2104.9 1305.79  2371.9 1292.54  2510.5 1285.53  2555.6 1284.45
  3263.7 1277.44  3461.2 1277.43  4551.8 1274.61  4755.3  1265.4  4906.6 1244.07
  4952.9  1231.9  5009.1 1242.73  5073.9  1256.5  5122.3 1277.24  5398.9 1285.33
    5676 1285.43  6563.8 1279.01  6770.7 1278.43  6902.5 1297.29  7231.4 1336.12
  7377.3 1344.56  8103.7  1361.5  8240.8 1365.19    9223 1379.36  9252.1 1379.48
#Mann= 20 ,-1 , 0
  1009.5     .07       0  1070.3     .12       0  1200.7     .07       0
    1767     .05       0  1856.6     .07       0  2371.9     .06       0
  2510.5     .05       0  2555.6     .06       0  3263.7     .05       0
  3461.2     .06       0  4551.8     .05       0  4906.6     .04       0
  5009.1     .12       0  5398.9     .07       0    5676     .05       0
  6563.8     .12       0  6902.5     .07       0  8103.7     .12       0
  8240.8     .07       0    9223     .07       0
Bank Sta=4906.6,5009.1
XS Rating Curve= 0 ,0
Exp/Cntr=0.3,0.1

Type RM Length L Ch R = 1 ,1952908 ,3631,3631,3631
BEGIN DESCRIPTION:
Guadalupe River - 101
END DESCRIPTION:
XS GIS Cut Line= 3
      2054996.26     13896782.01      2060030.99     13893101.45
      2062808.73     13892094.52
#Sta/Elev= 30
  1926.5 1364.94  2074.1 1362.64  2495.5 1350.76  4542.1 1302.08  4627.8 1258.08
  4822.4 1271.38  4893.4 1261.79  4943.6 1242.58  4994.4 1227.88  5058.7 1237.26
    5322 1269.81  5529.6 1276.29  6677.7 1275.76  6923.7 1275.77  7181.8 1279.26
  7333.6  1306.4  7448.6 1315.63  8137.3 1319.38  8513.2  1318.2    8684 1317.75
  9712.9 1322.25    9785 1322.77   10001 1324.34 10421.2  1327.4   10529 1328.53
 10633.2 1330.51 10776.6 1334.02 10845.3 1335.46 10951.3 1341.75 11117.7 1342.44
#Mann= 20 ,-1 , 0
  1926.5     .07       0  2074.1     .07       0  2495.5     .12       0
  4943.6     .04       0  5058.7     .12       0  6677.7     .07       0
  6923.7     .07       0  7181.8     .12       0  8137.3     .07       0
  8513.2     .12       0    8684     .07       0  9712.9     .07       0
    9785     .12       0   10001     .12       0 10421.2     .07       0
   10529     .07       0 10633.2     .12       0 10776.6     .07       0
 10845.3     .05       0 10951.3     .07       0
Bank Sta=4943.6,5058.7
XS Rating Curve= 0 ,0
Exp/Cntr=0.3,0.1

Type RM Length L Ch R = 1 ,1949277 ,3738,3738,3738
BEGIN DESCRIPTION:
Guadalupe River - 100
END DESCRIPTION:
XS GIS Cut Line= 5
      2060586.54     13900393.07      2060447.66     13898622.28
       2059267.1     13895705.62      2060030.99     13893726.45
      2062496.23      13892372.3
#Sta/Elev= 30
  1058.7 1349.89  1276.1 1346.73    1927    1338  2025.9  1336.8  3105.5 1335.04
    4310 1333.69    4817 1318.74  4870.9 1308.05  4924.9 1250.55    4968 1230.32
  5006.6 1220.56    5069 1229.11  5302.2 1261.01    6103 1270.47  6475.2 1262.47
  6549.5 1286.29  6624.1  1302.9  6772.1 1308.32  7394.7 1315.94  8074.3 1318.08
  9089.2 1320.35  9113.2 1320.44  9409.1 1322.59 10402.4 1327.09 10631.2 1327.94
 10652.5 1327.81 10745.6 1329.92 10845.9 1332.88   10860 1333.01 10915.6 1333.52
#Mann= 20 ,-1 , 0
  1058.7     .05       0  1276.1     .07       0    1927     .05       0
  2025.9     .07       0  3105.5     .12       0    4968     .04       0
    5069     .07       0  6549.5     .12       0  6772.1     .07       0
  7394.7     .05       0  8074.3     .07       0  9089.2     .12       0
  9113.2     .07       0  9409.1     .07       0 10402.4     .05       0
 10631.2     .07       0 10652.5     .05       0 10745.6     .12       0
 10845.9     .05       0   10860     .12       0
Bank Sta=4968,5069
XS Rating Curve= 0 ,0
Exp/Cntr=0.3,0.1

Type RM Length L Ch R = 1 ,1945539 ,6820,6820,6820
BEGIN DESCRIPTION:
Guadalupe River - 99
END DESCRIPTION:
XS GIS Cut Line= 5
      2060655.99     13900219.49      2060482.38      13898170.9
      2061940.71     13896886.17      2063190.71     13894247.28
      2063051.82     13891990.38
#Sta/Elev= 30
  -422.7 1346.01  -181.9 1343.49   467.4 1331.48   677.1 1332.42  1535.6 1333.55
  2132.6  1316.1  2671.3 1298.75  2945.6 1290.27  3493.5 1271.84  3715.8 1260.64
  4513.7 1263.22  4644.4 1261.57    4767 1260.78  4886.3  1248.7  4983.3 1228.89
  5008.2  1218.6    5085  1221.6    5105  1232.3  5181.9 1253.18  5204.6 1276.71
  5210.2 1293.72  5255.7  1319.2  5368.4 1326.11  5606.1  1333.5  6189.9 1333.48
  6634.3 1335.11    7433 1331.86  8124.2 1334.56  8537.1 1341.06  8757.9  1342.7
#Mann= 20 ,-1 , 0
  -422.7     .07       0  -181.9     .12       0   467.4     .07       0
   677.1     .07       0  1535.6     .07       0  2132.6     .07       0
  2671.3     .12       0  2945.6     .07       0  3493.5     .05       0
  4513.7     .07       0  4644.4     .05       0  4983.3     .04       0
    5105     .05       0  5368.4     .05       0  5606.1     .07       0
  6189.9     .07       0  6634.3     .05       0    7433     .12       0
  8124.2     .07       0  8537.1     .07       0
Bank Sta=4983.3,5105
XS Rating Curve= 0 ,0
Exp/Cntr=0.3,0.1

Type RM Length L Ch R = 1 ,1938719 ,5012,5012,5012
BEGIN DESCRIPTION:
Guadalupe River - 98
END DESCRIPTION:
XS GIS Cut Line= 4
      2065274.05     13901643.08      2065378.21     13896018.12
      2063468.49     13893413.95      2063294.93     13892129.61
#Sta/Elev= 30
  3481.7 1364.23  4368.9 1354.59    4730 1343.81    4770 1325.72    4870 1243.31
    4930 1226.34    4950 1212.83  4988.2 1209.71  5036.7 1212.71  5050.1 1221.97
  5090.1 1224.53  5190.1 1253.68  6211.5 1253.32  6538.3 1263.67  6774.4 1276.89
  7078.1 1288.52  7907.7 1307.03  8251.4 1304.49  8481.6 1298.65  8620.7  1279.4
  8910.6 1304.85    9129 1313.54  9439.6 1319.61 10129.6 1325.95 11166.3 1331.55
 12103.2 1342.15 12327.4 1340.85 12927.4 1333.55 13326.1 1338.79   13633 1342.25
#Mann= 20 ,-1 , 0
  3481.7     .07       0  4368.9     .07       0    4930     .04       0
  5050.1     .07       0  6211.5     .12       0  6538.3     .07       0
  6774.4     .12       0  7078.1     .12       0  7907.7     .07       0
  8251.4     .07       0  8481.6     .12       0  8910.6     .12       0
    9129     .07       0  9439.6     .12       0 10129.6     .07       0
 11166.3     .07       0 12103.2     .07       0 12327.4     .12       0
 12927.4     .12       0 13326.1     .07       0
Bank Sta=4930,5050.1
XS Rating Curve= 0 ,0
Exp/Cntr=0.3,0.1

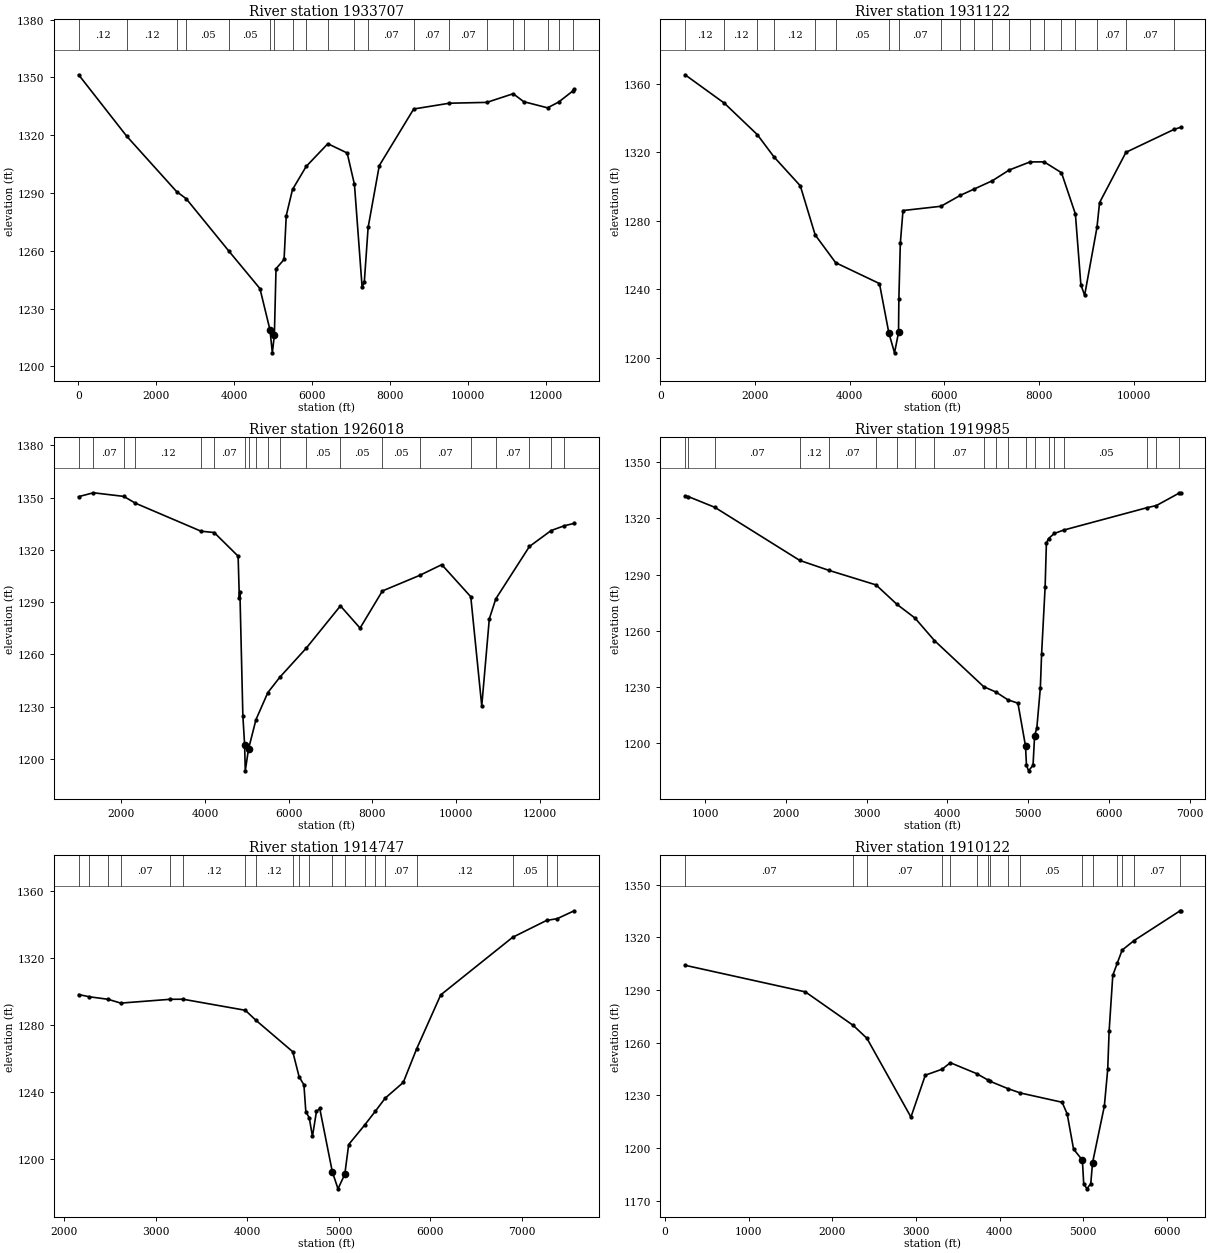
Type RM Length L Ch R = 1 ,1933707 ,2585,2585,2585
BEGIN DESCRIPTION:
Guadalupe River - 97
END DESCRIPTION:
XS GIS Cut Line= 4
      2068329.61     13901400.04      2069787.93     13898413.95
      2063607.38     13893309.78      2063364.32     13891955.61
#Sta/Elev= 30
     5.8 1351.41  1236.4  1319.6  2520.9 1290.75  2765.8 1287.08  3866.7 1259.74
  4658.2 1240.42  4914.9 1219.04  4976.1 1207.07  5028.2 1216.31  5070.6 1250.74
  5277.1 1255.55  5333.1 1278.33  5493.8 1291.87  5845.1 1303.85  6399.6 1315.62
  6896.4 1310.81  7082.8 1294.48  7279.4 1241.17  7336.8 1244.09  7433.4 1272.15
  7719.8 1304.26  8603.2 1333.65  9518.9 1336.65 10479.1 1337.08 11155.4 1341.57
 11427.1 1337.44 12037.3 1334.26 12322.2 1337.24 12681.2 1342.92 12720.5  1343.9
#Mann= 20 ,-1 , 0
     5.8     .12       0  1236.4     .12       0  2520.9     .05       0
  2765.8     .05       0  3866.7     .05       0  4914.9     .04       0
  5028.2     .05       0  5493.8     .07       0  5845.1     .07       0
  6399.6     .07       0  7082.8     .12       0  7433.4     .07       0
  8603.2     .07       0  9518.9     .07       0 10479.1     .05       0
 11155.4     .05       0 11427.1     .07       0 12037.3     .12       0
 12322.2     .07       0 12681.2     .07       0
Bank Sta=4914.9,5028.2
XS Rating Curve= 0 ,0
Exp/Cntr=0.3,0.1

Type RM Length L Ch R = 1 ,1931122 ,5104,5104,5104
BEGIN DESCRIPTION:
Guadalupe River - 96
END DESCRIPTION:
XS GIS Cut Line= 5
      2074024.02     13898518.11      2070794.88      13896920.9
      2070378.21     13895740.34      2067357.38     13896018.12
      2065274.01     13894490.31
#Sta/Elev= 30
   522.8 1365.37  1354.1 1348.74  2048.8 1330.42  2400.1 1317.44  2956.9 1300.54
  3271.5 1271.85  3704.7 1255.63    4630 1243.44  4828.6 1214.59  4948.4 1202.99
    5033 1214.87  5039.9 1234.17  5070.8 1266.94  5127.3 1286.09  5929.3 1288.58
  6341.8    1295  6618.2 1298.48  7016.8 1303.51  7370.8 1309.74  7810.9 1314.47
  8108.7 1314.52  8476.3 1308.18  8770.3 1284.09  8886.2 1242.76  8965.7 1236.58
  9226.1  1276.2  9281.3 1290.71  9839.6 1320.11 10859.3 1333.52 10994.4 1334.67
#Mann= 20 ,-1 , 0
   522.8     .12       0  1354.1     .12       0  2048.8     .07       0
  2400.1     .12       0  3271.5     .12       0  3704.7     .05       0
  4828.6     .04       0    5033     .07       0  5929.3     .05       0
  6341.8     .05       0  6618.2     .05       0  7016.8     .12       0
  7370.8     .07       0  7810.9     .05       0  8108.7     .07       0
  8476.3     .05       0  8770.3     .12       0  9226.1     .07       0
  9839.6     .07       0 10859.3     .05       0
Bank Sta=4828.6,5033
XS Rating Curve= 0 ,0
Exp/Cntr=0.3,0.1

Type RM Length L Ch R = 1 ,1926018 ,6033,6033,6033
BEGIN DESCRIPTION:
Guadalupe River - 95
END DESCRIPTION:
XS GIS Cut Line= 5
      2075100.41     13894976.44      2072114.32     13893309.78
       2070204.6     13895601.45      2067426.82     13895844.51
       2065204.6     13894386.17
#Sta/Elev= 30
   978.6 1350.58  1332.4 1352.79  2056.9 1350.72    2335 1346.83  3905.4 1330.73
    4220 1329.97  4792.3 1316.41    4821 1292.56  4834.7 1296.07  4905.6 1224.83
  4948.5 1207.76  4963.1 1193.18    5041 1205.73  5219.4 1222.59  5503.4 1238.12
  5791.5 1246.97  6421.8 1263.62  7238.6 1287.87  7708.1 1275.11  8242.2 1296.43
  9138.6 1305.43  9661.9 1311.54 10355.3 1293.12   10618 1230.41 10798.8 1280.46
 10954.4 1291.93 11757.8 1321.96 12278.3 1331.13 12594.9 1333.88 12827.8 1335.22
#Mann= 20 ,-1 , 0
   978.6     .07       0  1332.4     .07       0  2056.9     .07       0
    2335     .12       0  3905.4     .12       0    4220     .07       0
  4948.5     .04       0    5041     .12       0  5219.4     .12       0
  5503.4     .07       0  5791.5     .12       0  6421.8     .05       0
  7238.6     .05       0  8242.2     .05       0  9138.6     .07       0
 10355.3     .12       0 10954.4     .07       0 11757.8     .05       0
 12278.3     .07       0 12594.9     .05       0
Bank Sta=4948.5,5041
XS Rating Curve= 0 ,0
Exp/Cntr=0.3,0.1

Type RM Length L Ch R = 1 ,1919985 ,5238,5238,5238
BEGIN DESCRIPTION:
Guadalupe River - 94
END DESCRIPTION:
XS GIS Cut Line= 3
      2071037.94     13892407.01      2068399.04     13892823.67
      2065379.08     13894524.57
#Sta/Elev= 30
   750.9 1331.98     788 1331.74  1118.4 1325.97  2171.2 1297.56  2527.6 1292.31
  3115.4 1284.48  3374.3  1274.1  3597.4 1266.78  3839.4 1254.71  4449.7 1230.04
  4600.3  1227.2  4748.6 1223.04  4873.2 1221.24  4967.2 1198.32    4979 1188.06
  5005.1 1185.06  5060.4 1188.06  5079.8 1203.88  5107.4 1208.03  5150.8 1229.32
  5166.7 1247.78    5210 1283.39  5225.9 1306.85  5251.9 1309.25  5324.3 1311.98
  5439.4 1313.78  6475.6  1325.8  6588.7 1326.91    6865 1333.44  6888.5 1333.73
#Mann= 20 ,-1 , 0
   750.9     .07       0     788     .05       0  1118.4     .07       0
  2171.2     .12       0  2527.6     .07       0  3115.4     .05       0
  3374.3     .07       0  3597.4     .12       0  3839.4     .07       0
  4449.7     .12       0  4600.3     .07       0  4748.6     .12       0
  4967.2     .04       0  5079.8     .05       0  5251.9     .05       0
  5324.3     .07       0  5439.4     .05       0  6475.6     .07       0
  6588.7     .07       0    6865     .05       0
Bank Sta=4967.2,5079.8
XS Rating Curve= 0 ,0
Exp/Cntr=0.3,0.1

Type RM Length L Ch R = 1 ,1914747 ,4625,4625,4625
BEGIN DESCRIPTION:
Guadalupe River - 93
END DESCRIPTION:
XS GIS Cut Line= 2
       2070621.3     13890983.42      2066178.43     13887894.24
#Sta/Elev= 30
  2159.1 1298.22  2276.3 1296.88    2480 1295.38  2619.3  1293.1  3156.5 1295.37
  3298.6 1295.42    3979 1288.82  4096.5 1282.78  4497.5 1264.06  4566.6 1249.15
  4619.2 1244.28  4640.2 1228.27  4677.8 1224.59  4712.3  1213.5  4756.3 1228.43
  4792.1 1230.19  4929.1 1192.46  4991.4 1182.22  5065.6 1190.91  5108.1 1208.67
  5282.6 1220.31  5399.1 1228.54  5506.6 1236.34  5704.2 1245.75  5849.4 1265.69
    6113    1298  6898.3 1332.38  7269.2 1342.46  7385.7 1343.52  7570.4 1348.22
#Mann= 20 ,-1 , 0
  2159.1     .05       0  2276.3     .07       0    2480     .05       0
  2619.3     .07       0  3156.5     .12       0  3298.6     .12       0
    3979     .07       0  4096.5     .12       0  4497.5     .12       0
  4566.6     .05       0  4677.8     .12       0  4929.1     .04       0
  5065.6     .12       0  5282.6     .07       0  5399.1     .12       0
  5506.6     .07       0  5849.4     .12       0  6898.3     .05       0
  7269.2     .05       0  7385.7     .12       0
Bank Sta=4929.1,5065.6
XS Rating Curve= 0 ,0
Exp/Cntr=0.3,0.1

Type RM Length L Ch R = 1 ,1910122 ,4468,4468,4468
BEGIN DESCRIPTION:
Guadalupe River - 92
END DESCRIPTION:
XS GIS Cut Line= 2
      2071003.21     13890879.23      2070169.94      13885011.6
#Sta/Elev= 30
   238.7 1304.05  1677.2  1288.9  2250.4 1269.76  2413.1 1262.45  2939.8 1217.56
  3111.5 1241.44    3311 1244.81    3411 1248.53    3724 1242.36  3857.9 1238.76
  3882.1 1238.04    4097 1233.82  4249.4 1231.29  4747.7 1226.01  4808.3 1219.37
  4884.3 1199.36  4990.1 1193.01  5005.8 1179.68  5044.1 1176.68  5090.5 1179.68
  5111.3 1191.48  5252.7 1223.77  5293.1 1244.75  5309.8 1266.48  5353.7 1298.33
    5407 1305.21  5465.4 1312.69  5609.1 1318.17  6155.2 1334.99  6165.2 1335.11
#Mann= 16 ,-1 , 0
   238.7     .07       0  2250.4     .12       0  2413.1     .07       0
    3311     .05       0    3411     .07       0    3724     .05       0
  3857.9     .12       0  3882.1     .05       0    4097     .07       0
  4249.4     .05       0  4990.1     .04       0  5111.3     .05       0
    5407     .07       0  5465.4     .05       0  5609.1     .07       0
  6155.2     .05       0
Bank Sta=4990.1,5111.3
XS Rating Curve= 0 ,0
Exp/Cntr=0.3,0.1

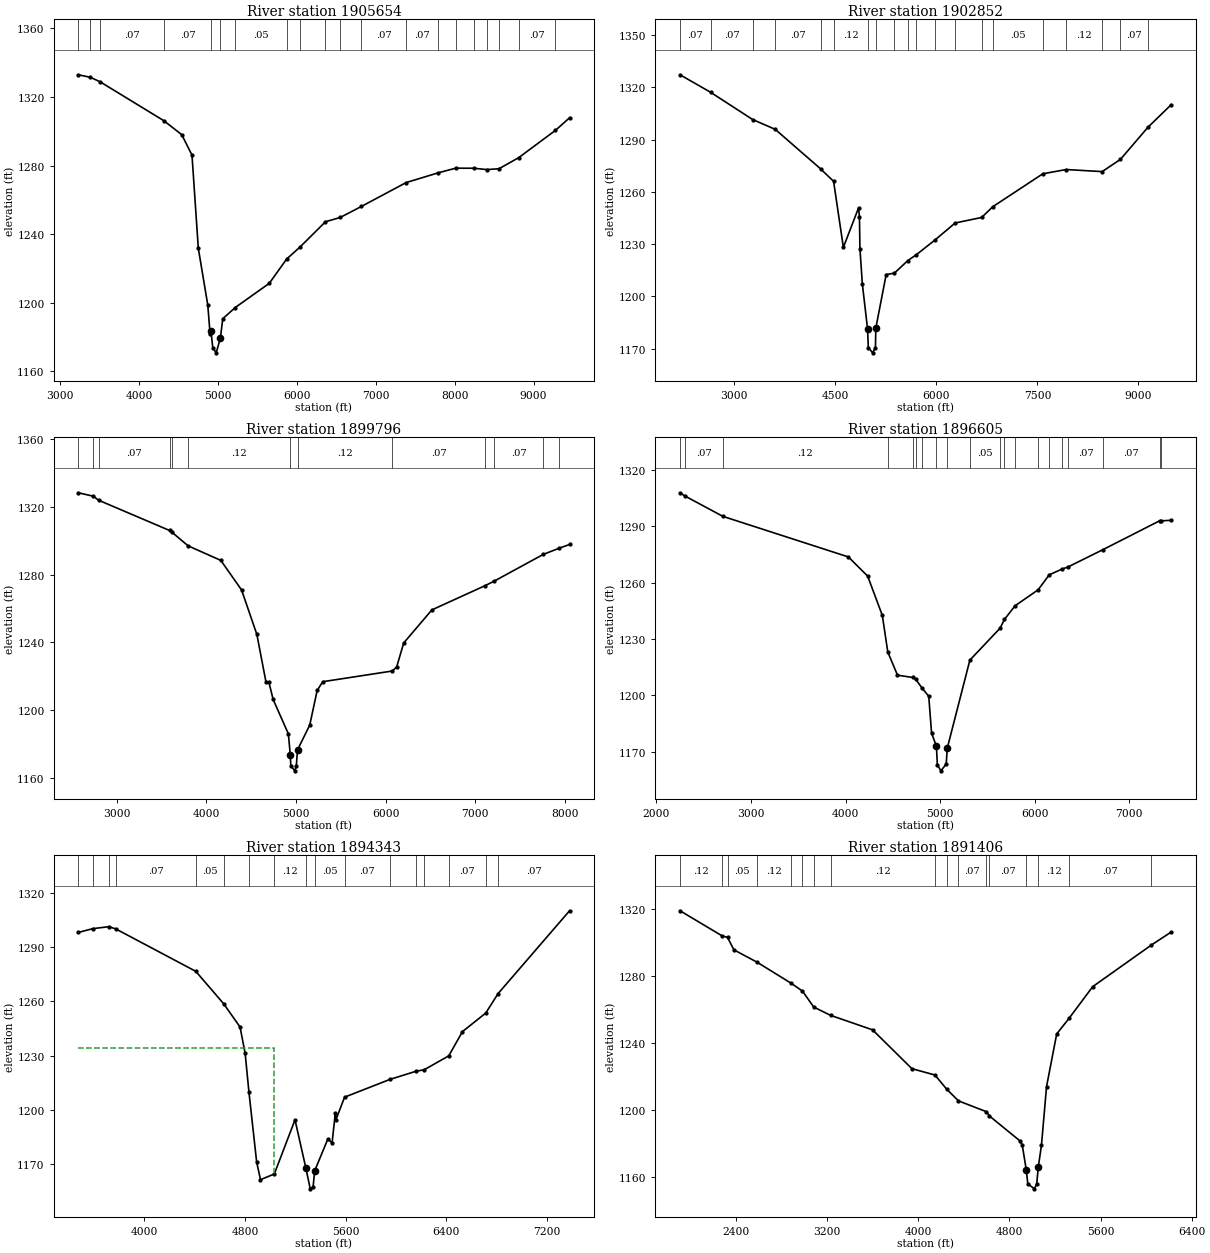
Type RM Length L Ch R = 1 ,1905654 ,2802,2802,2802
BEGIN DESCRIPTION:
Guadalupe River - 91
END DESCRIPTION:
XS GIS Cut Line= 4
      2073850.43     13889594.55      2073850.43     13886261.17
       2072704.6     13885844.51      2071454.57     13884733.37
#Sta/Elev= 30
  3230.4 1332.93  3381.4 1331.46  3503.8 1328.88  4315.2  1306.1    4540 1298.02
    4670  1286.1    4750 1231.81    4870 1198.73    4900 1181.53    4910 1183.55
  4933.8 1173.83  4976.7 1170.83    5030 1179.38    5060 1190.71  5218.4 1197.25
    5650 1211.37  5870.2 1225.54  6037.5 1232.44  6362.1 1247.26  6547.7 1249.73
  6817.5 1256.18  7385.2 1270.11  7794.3 1275.82  8012.8 1278.48  8239.6 1278.45
  8407.9 1277.67  8561.3 1278.16  8810.9 1284.61  9276.1  1300.5  9455.5 1307.86
#Mann= 20 ,-1 , 0
  3230.4     .12       0  3381.4     .12       0  3503.8     .07       0
  4315.2     .07       0    4910     .04       0    5030     .12       0
  5218.4     .05       0  5870.2     .07       0  6037.5     .07       0
  6362.1     .05       0  6547.7     .07       0  6817.5     .07       0
  7385.2     .07       0  7794.3     .07       0  8012.8     .07       0
  8239.6     .12       0  8407.9     .07       0  8561.3     .12       0
  8810.9     .07       0  9276.1     .07       0
Bank Sta=4910,5030
XS Rating Curve= 0 ,0
Exp/Cntr=0.3,0.1

Type RM Length L Ch R = 1 ,1902852 ,3056,3056,3056
BEGIN DESCRIPTION:
Guadalupe River - 90
END DESCRIPTION:
XS GIS Cut Line= 3
      2078260.16     13886886.17      2072878.21      13885670.9
      2071524.08     13884525.09
#Sta/Elev= 30
  2194.3 1327.28  2646.6 1317.26  3271.9 1301.58    3607 1295.96  4279.7 1273.29
  4474.1 1266.06    4619 1228.16  4844.5 1250.84  4857.7 1245.77    4865 1227.43
    4901  1207.1  4977.8 1181.44  4989.8 1170.59  5053.5 1167.59  5095.3 1170.59
  5100.8 1181.81  5254.6 1212.56  5375.6 1213.33  5576.3 1220.59  5703.7 1223.97
    5986 1232.62  6278.7 1242.16  6671.8 1245.34  6836.6 1251.49  7580.2 1270.42
  7927.7 1272.86  8461.6 1271.67  8732.9 1278.72  9143.5 1297.26  9485.6 1310.07
#Mann= 20 ,-1 , 0
  2194.3     .07       0  2646.6     .07       0  3271.9     .07       0
    3607     .07       0  4279.7     .07       0  4474.1     .12       0
  4977.8     .04       0  5100.8     .12       0  5375.6     .07       0
  5576.3     .12       0  5703.7     .07       0    5986     .12       0
  6278.7     .07       0  6671.8     .07       0  6836.6     .05       0
  7580.2     .07       0  7927.7     .12       0  8461.6     .12       0
  8732.9     .07       0  9143.5     .07       0
Bank Sta=4977.8,5100.8
XS Rating Curve= 0 ,0
Exp/Cntr=0.3,0.1

Type RM Length L Ch R = 1 ,1899796 ,3191,3191,3191
BEGIN DESCRIPTION:
Guadalupe River - 89
END DESCRIPTION:
XS GIS Cut Line= 3
      2077149.03     13883136.18      2073989.32     13883969.51
      2071871.26     13883344.51
#Sta/Elev= 30
  2574.6 1328.39    2742 1326.34  2799.5    1324  3590.7 1306.13  3619.4    1305
  3798.6 1297.02  4162.2 1288.47  4393.6 1271.02  4564.4 1244.72  4665.3  1216.8
  4698.9 1216.44  4745.9 1206.31    4916 1185.96  4936.7 1173.59  4943.4 1167.05
  4988.2 1164.17  5004.2 1167.05  5017.6 1176.57  5153.9 1191.18  5236.6 1211.66
  5299.6 1216.82  6073.7 1223.12  6123.2 1225.53  6201.4 1239.69  6515.7 1259.22
  7110.7 1273.58  7212.5 1276.26  7756.6 1291.97  7936.3 1295.68  8050.7 1297.85
#Mann= 13 ,-1 , 0
  2574.6     .07       0    2742     .05       0  2799.5     .07       0
  3590.7     .12       0  3619.4     .07       0  3798.6     .12       0
  4936.7     .04       0  5017.6     .12       0  6073.7     .07       0
  7110.7     .05       0  7212.5     .07       0  7756.6     .12       0
  7936.3     .07       0
Bank Sta=4936.7,5017.6
XS Rating Curve= 0 ,0
Exp/Cntr=0.3,0.1

Type RM Length L Ch R = 1 ,1896605 ,2262,2262,2262
BEGIN DESCRIPTION:
Guadalupe River - 88
END DESCRIPTION:
XS GIS Cut Line= 3
      2076385.18     13881330.63      2074405.99     13880775.06
      2071559.38     13882094.22
#Sta/Elev= 30
  2248.9 1307.88  2297.5 1306.25  2701.5 1295.33  4028.8 1273.72  4232.9  1263.5
    4388 1242.56  4445.4 1223.13  4548.2 1210.77  4710.1 1209.54  4741.7 1208.55
  4804.6 1204.11  4878.8 1199.51  4908.6 1179.88    4960 1172.92  4969.6 1163.05
  5007.4 1159.83  5063.3 1163.46  5074.5  1171.9  5313.5 1218.78  5633.1 1235.79
  5679.5  1240.5  5792.3 1247.74    6035  1256.2  6153.1 1264.22  6283.1 1267.14
  6352.9 1268.43  6720.8 1277.61  7319.9 1292.96  7339.3 1292.94    7442 1293.24
#Mann= 20 ,-1 , 0
  2248.9     .12       0  2297.5     .07       0  2701.5     .12       0
  4445.4     .05       0  4710.1     .12       0  4741.7     .05       0
  4804.6     .12       0    4960     .04       0  5074.5     .12       0
  5313.5     .05       0  5633.1     .07       0  5679.5     .05       0
  5792.3     .07       0    6035     .05       0  6153.1     .07       0
  6283.1     .05       0  6352.9     .07       0  6720.8     .07       0
  7319.9     .12       0  7339.3     .07       0
Bank Sta=4960,5074.5
XS Rating Curve= 0 ,0
Exp/Cntr=0.3,0.1

Type RM Length L Ch R = 1 ,1894343 ,2937,2937,2937
BEGIN DESCRIPTION:
Guadalupe River - 87
END DESCRIPTION:
XS GIS Cut Line= 4
      2074755.05     13878342.88      2073921.73     13878954.85
      2072593.61     13879189.22      2071098.07     13878916.12
#Sta/Elev= 30
    3477 1298.08  3591.1 1300.15  3719.3 1301.25  3774.1 1300.01  4410.1 1276.58
  4631.1 1258.71  4761.4 1245.88    4802 1231.29  4832.3 1209.83  4893.4 1171.33
  4923.9  1161.6  5033.6 1164.74  5198.1 1194.64    5284 1168.18  5319.2 1156.55
  5341.6 1157.35  5354.5 1166.49  5459.1 1184.03  5492.6 1181.88  5518.4 1198.26
  5523.4 1194.71    5592 1207.15  5953.1 1216.96  6159.1 1221.43  6224.5 1222.27
  6419.9 1229.94    6529 1243.35  6713.7 1253.55  6812.1 1264.33  7379.8 1310.02
#Mann= 17 ,-1 , 0
    3477     .12       0  3591.1     .07       0  3719.3     .05       0
  3774.1     .07       0  4410.1     .05       0  4631.1     .12       0
  4832.3     .07       0  5033.6     .12       0    5284     .04       0
  5354.5     .05       0    5592     .07       0  5953.1     .05       0
  6159.1     .07       0  6224.5     .05       0  6419.9     .07       0
  6713.7     .05       0  6812.1     .07       0
#XS Ineff= 2 , 0
       0 5032.97  1234.3               0
Permanent Ineff=
       F       F
Bank Sta=5284,5354.5
XS Rating Curve= 0 ,0
Exp/Cntr=0.3,0.1

Type RM Length L Ch R = 1 ,1891406 ,2567,2567,2567
BEGIN DESCRIPTION:
Guadalupe River - 86
END DESCRIPTION:
XS GIS Cut Line= 6
      2074654.48     13876265.95      2073112.61     13876449.74
      2072937.48     13876588.85      2071873.42     13876891.16
      2071309.21     13877176.72      2070765.56     13877759.01
#Sta/Elev= 30
    1908 1319.07  2278.1 1304.03  2324.7 1303.18  2380.8 1295.69  2583.9 1288.31
  2882.7 1275.73  2982.3 1271.04  3081.9 1261.44  3230.1 1256.48  3598.2 1247.82
  3943.3 1224.59  4145.8 1220.78  4249.1  1212.3  4352.5  1205.3  4597.1 1198.85
  4623.3 1196.32  4889.7 1181.49  4912.1 1178.94  4947.2  1164.2    4961 1155.67
  5018.8 1152.67  5039.3 1155.67    5053 1165.71  5080.9 1178.79  5125.4 1213.82
  5214.7 1245.38  5324.9 1254.86  5530.6 1273.66  6046.8 1298.62  6219.6 1306.33
#Mann= 17 ,-1 , 0
    1908     .12       0  2278.1     .07       0  2324.7     .05       0
  2583.9     .12       0  2882.7     .07       0  2982.3     .12       0
  3081.9     .05       0  3230.1     .12       0  4145.8     .07       0
  4249.1     .05       0  4352.5     .07       0  4597.1     .05       0
  4623.3     .07       0  4947.2     .04       0    5053     .12       0
  5324.9     .07       0  6046.8     .05       0
Bank Sta=4947.2,5053
XS Rating Curve= 0 ,0
Exp/Cntr=0.3,0.1