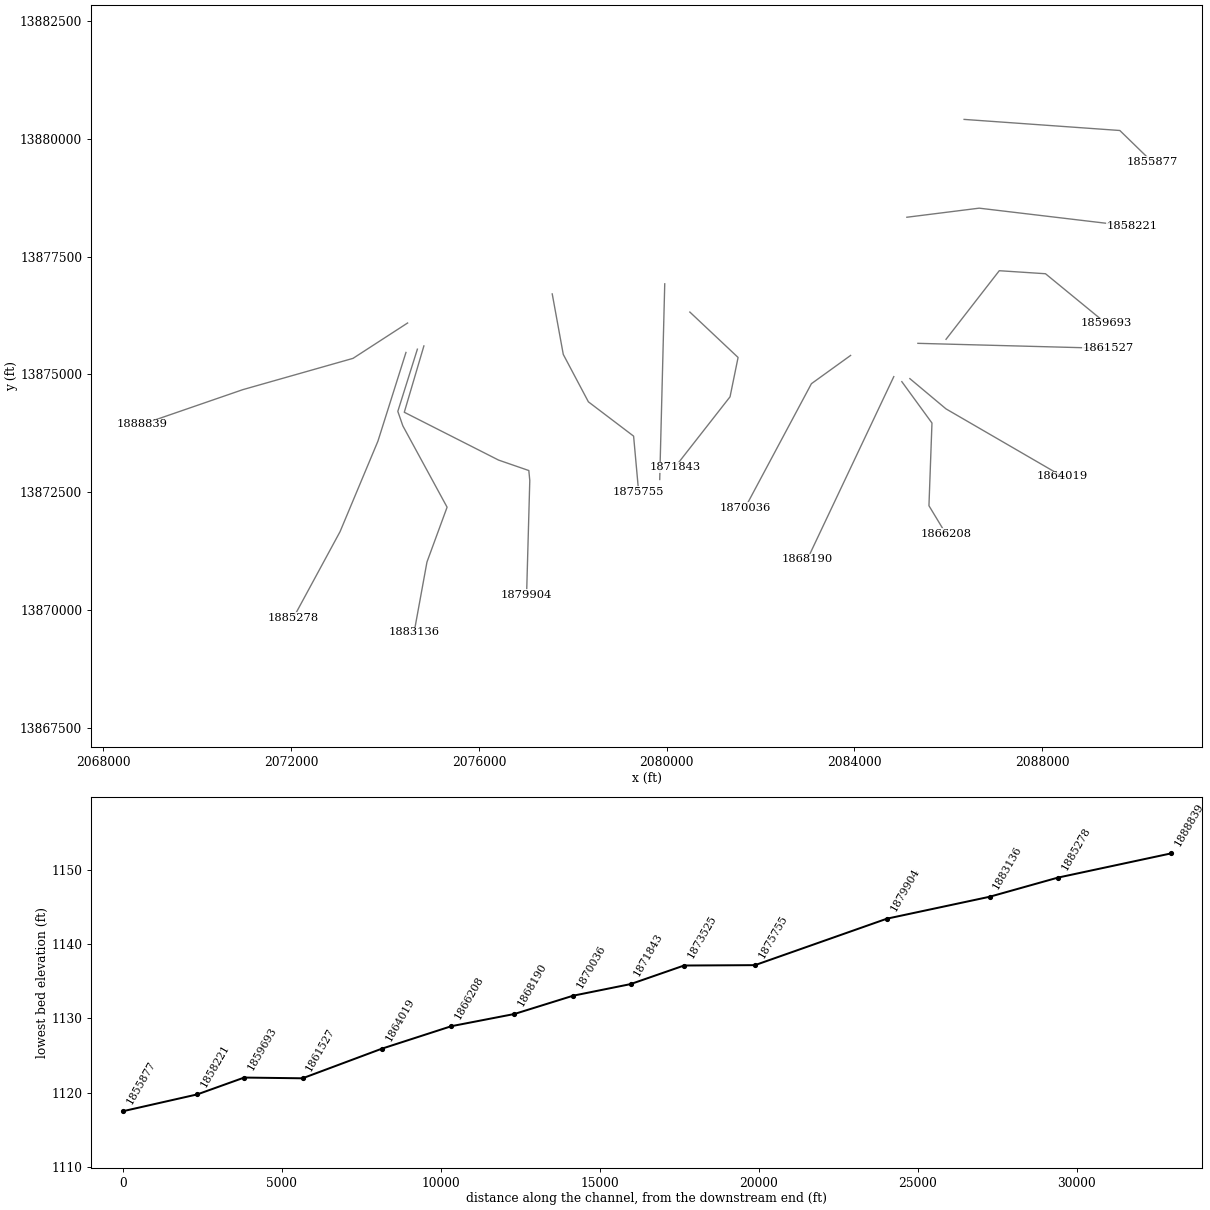
HEC-RAS study Guadalupe River.prj: Guadalupe River Base Level Engineering

--- Guadalupe River.g01 (geometry) --- (continued)

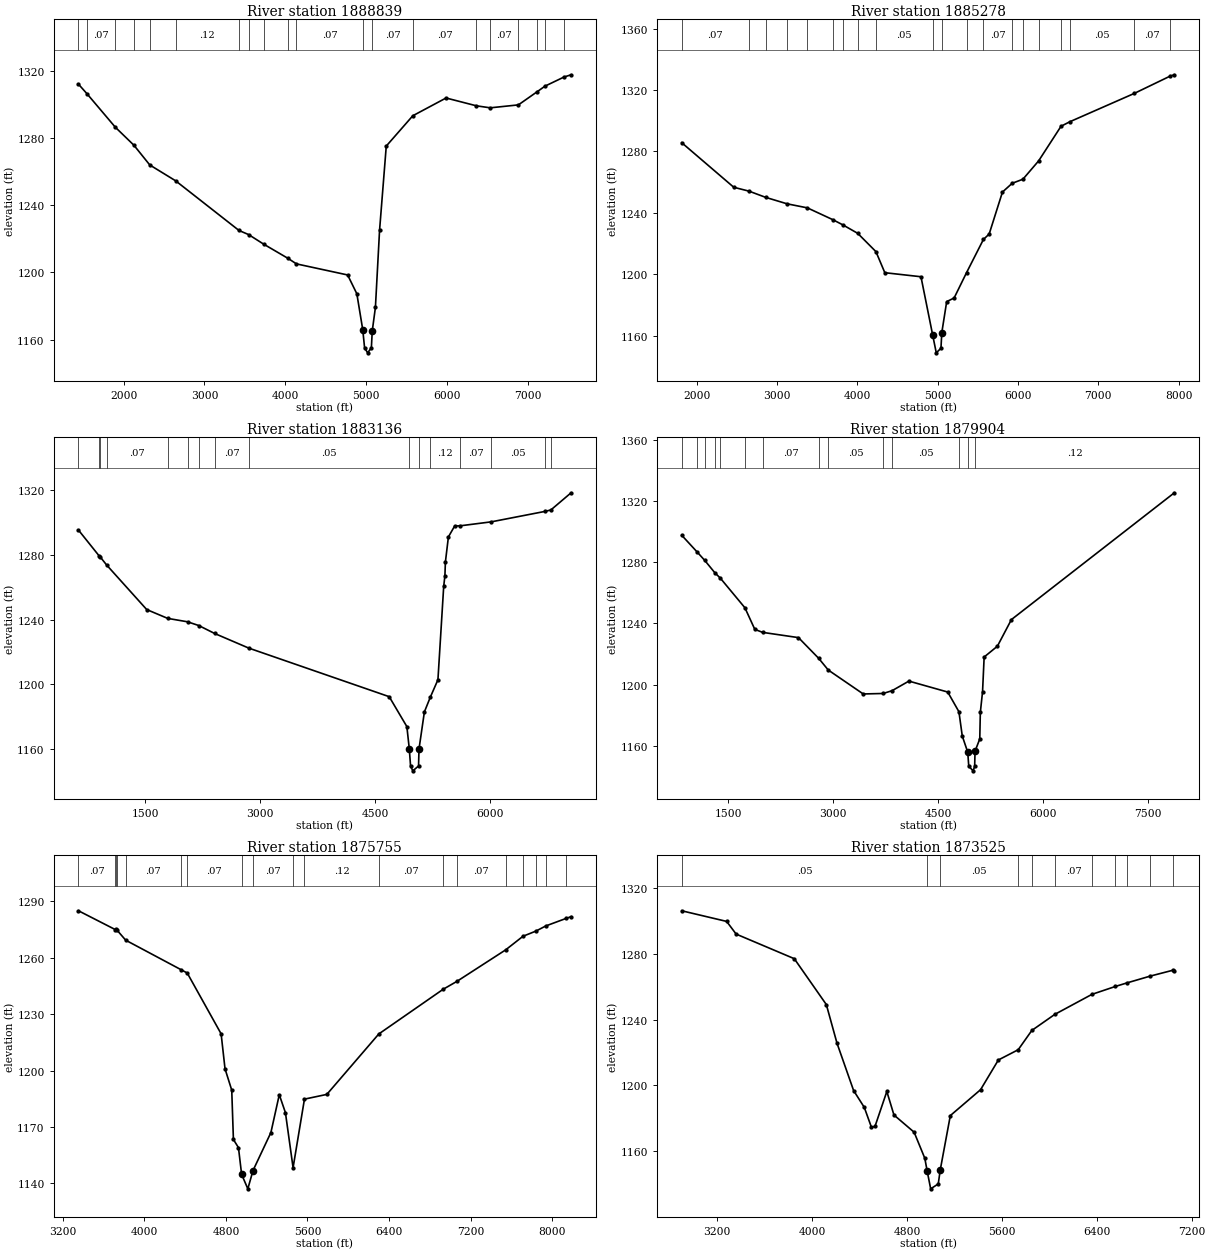
Type RM Length L Ch R = 1 ,1888839 ,3561,3561,3561
BEGIN DESCRIPTION:
Guadalupe River - 85
END DESCRIPTION:
XS GIS Cut Line= 4
      2074480.84     13876092.34      2073318.58     13875342.27
      2070969.77     13874677.98      2068821.79     13873939.79
#Sta/Elev= 30
  1440.8 1312.08  1543.4 1306.54  1896.6 1286.47  2127.1 1275.73  2322.8 1264.01
  2642.3 1254.59    3427 1225.01    3546 1222.56  3731.6 1216.89  4036.1 1208.33
  4137.7 1205.12  4771.1 1198.53  4885.2 1187.32  4958.2 1165.94  4980.9 1155.17
  5018.4 1152.17  5064.9 1155.17  5075.8 1165.17    5115 1179.26  5166.1 1225.02
  5249.2 1275.25  5577.4 1293.29  5989.1 1303.87  6365.3 1299.21    6536 1298.02
  6884.1 1299.77  7110.2 1307.39  7213.3 1310.93  7448.1 1316.34  7536.3 1317.69
#Mann= 20 ,-1 , 0
  1440.8     .12       0  1543.4     .07       0  1896.6     .12       0
  2127.1     .07       0  2322.8     .05       0  2642.3     .12       0
    3427     .07       0    3546     .12       0  3731.6     .07       0
  4036.1     .05       0  4137.7     .07       0  4958.2     .04       0
  5075.8     .07       0  5577.4     .07       0  6365.3     .05       0
    6536     .07       0  6884.1     .05       0  7110.2     .07       0
  7213.3     .05       0  7448.1     .07       0
Bank Sta=4958.2,5075.8
XS Rating Curve= 0 ,0
Exp/Cntr=0.3,0.1

Type RM Length L Ch R = 1 ,1885278 ,2142,2142,2142
BEGIN DESCRIPTION:
Guadalupe River - 84
END DESCRIPTION:
XS GIS Cut Line= 4
      2074446.12     13875467.34      2073849.04     13873585.82
      2073042.66     13871666.89       2072050.3     13869842.36
#Sta/Elev= 30
  1815.5 1285.68  2463.5 1256.66  2653.7 1254.14  2862.2 1250.07  3127.4  1245.9
  3379.5 1243.27    3696 1235.59    3825 1232.09  4006.1 1226.69  4233.1 1214.78
  4343.6 1201.07  4793.7 1198.44  4940.2 1160.28  4984.1 1148.91  5042.5 1151.91
  5052.9 1162.04  5113.7 1182.25  5206.3 1184.61    5361  1201.1    5571  1222.7
  5642.7 1226.24  5807.9 1253.55  5929.1 1259.26  6062.9 1261.92    6258 1273.82
  6537.4 1296.39  6648.3 1299.36  7448.7 1317.75  7889.1 1328.86  7947.9 1329.89
#Mann= 20 ,-1 , 0
  1815.5     .07       0  2653.7     .12       0  2862.2     .07       0
  3127.4     .12       0  3379.5     .12       0    3696     .05       0
    3825     .07       0  4006.1     .12       0  4233.1     .05       0
  4940.2     .04       0  5052.9     .05       0    5361     .12       0
    5571     .07       0  5929.1     .12       0  6062.9     .07       0
    6258     .07       0  6537.4     .07       0  6648.3     .05       0
  7448.7     .07       0  7889.1     .12       0
Bank Sta=4940.2,5052.9
XS Rating Curve= 0 ,0
Exp/Cntr=0.3,0.1

Type RM Length L Ch R = 1 ,1883136 ,3232,3232,3232
BEGIN DESCRIPTION:
Guadalupe River - 83
END DESCRIPTION:
XS GIS Cut Line= 6
      2074689.17     13875536.76      2074272.51     13874217.34
      2074379.61     13873910.31      2075322.09     13872184.74
      2074893.31     13871021.21      2074619.88     13869530.64
#Sta/Elev= 30
   628.1 1295.39   898.6 1279.36   907.6 1279.01   997.1 1273.69    1519 1246.19
  1792.7 1240.73  2051.9 1238.61  2198.1 1236.31  2405.9 1231.38  2850.3 1222.35
    4685 1192.25  4915.6 1173.72  4947.3 1159.95  4963.9 1149.34    4993 1146.34
  5068.1 1149.34  5074.1 1159.88  5144.5 1182.84  5220.5  1191.8  5321.2 1202.73
  5396.5 1260.54  5412.3 1267.08  5418.6 1275.59  5457.9 1291.17  5539.6 1297.92
  5615.6 1298.06    6018  1300.5  6720.2 1306.97  6795.9 1307.86  7059.9 1318.49
#Mann= 16 ,-1 , 0
   628.1     .12       0   898.6     .07       0   907.6     .12       0
   997.1     .07       0  1792.7     .12       0  2051.9     .07       0
  2198.1     .05       0  2405.9     .07       0  2850.3     .05       0
  4947.3     .04       0  5074.1     .07       0  5220.5     .12       0
  5615.6     .07       0    6018     .05       0  6720.2     .07       0
  6795.9     .05       0
Bank Sta=4947.3,5074.1
XS Rating Curve= 0 ,0
Exp/Cntr=0.3,0.1

Type RM Length L Ch R = 1 ,1879904 ,4149,4149,4149
BEGIN DESCRIPTION:
Guadalupe River - 82
END DESCRIPTION:
XS GIS Cut Line= 6
      2074828.06     13875606.19      2074410.49     13874198.74
      2076419.29     13873183.98      2077063.09     13872962.43
      2077083.68     13872751.26      2077015.59     13870329.18
#Sta/Elev= 30
   836.6 1297.85  1060.2  1286.7    1166 1281.32  1309.5 1273.26  1386.3 1269.81
  1738.9  1250.3  1880.1 1236.15  1991.8 1234.18  2503.6 1230.74  2791.5  1217.2
  2929.1 1209.48  3428.7 1193.79  3713.5 1194.12  3839.7 1195.93  4080.8 1202.23
  4635.3 1195.05  4794.9 1182.14  4842.8 1166.21  4920.8 1155.62  4935.4 1146.39
  4997.8 1143.39  5019.7 1146.39  5024.9 1156.25  5092.6  1164.3  5100.6 1181.65
  5132.4 1195.32  5155.1 1218.02    5344 1225.09  5544.6 1242.57  7871.3 1325.71
#Mann= 14 ,-1 , 0
   836.6     .07       0  1060.2     .12       0    1166     .07       0
  1309.5     .12       0  1386.3     .07       0  1738.9     .12       0
  1991.8     .07       0  2791.5     .12       0  2929.1     .05       0
  3713.5     .07       0  3839.7     .05       0  4794.9     .12       0
  4920.8     .04       0  5024.9     .12       0
Bank Sta=4920.8,5024.9
XS Rating Curve= 0 ,0
Exp/Cntr=0.3,0.1

Type RM Length L Ch R = 1 ,1875755 ,2230,2230,2230
BEGIN DESCRIPTION:
Guadalupe River - 81
END DESCRIPTION:
XS GIS Cut Line= 5
      2077561.68     13876709.41      2077797.07      13875425.5
      2078332.03     13874419.76      2079294.98     13873692.21
      2079401.97     13872515.32
#Sta/Elev= 30
  3353.7 1285.06  3713.2  1275.1  3720.7 1275.12  3732.4 1274.71    3817 1269.41
  4357.9 1253.78  4420.7 1251.95  4753.1  1219.6  4791.4 1200.99  4857.3 1189.64
  4873.7 1163.39  4923.3 1159.06  4954.1 1144.88  5015.1 1137.14  5065.8 1146.86
  5241.5 1167.08  5323.8 1187.21    5384 1177.67  5459.1  1148.4  5570.7 1184.86
  5790.2 1187.38  6300.1 1219.53  6931.7 1243.31  7065.7 1247.48  7544.6 1264.26
  7715.1 1271.51  7840.1 1274.22  7938.6 1276.99  8135.6 1280.96  8186.8 1281.93
#Mann= 19 ,-1 , 0
  3353.7     .07       0  3713.2     .05       0  3720.7     .12       0
  3732.4     .05       0    3817     .07       0  4357.9     .12       0
  4420.7     .07       0  4954.1     .04       0  5065.8     .07       0
  5459.1      .1       0  5570.7     .12       0  6300.1     .07       0
  6931.7     .05       0  7065.7     .07       0  7544.6     .12       0
  7715.1     .07       0  7840.1     .12       0  7938.6     .07       0
  8135.6     .05       0
Bank Sta=4954.1,5065.8
XS Rating Curve= 0 ,0
Exp/Cntr=0.3,0.1

Type RM Length L Ch R = 1 ,1873525 ,1682,1682,1682
BEGIN DESCRIPTION:
Guadalupe River - 80
END DESCRIPTION:
XS GIS Cut Line= 2
      2079958.34     13876923.45      2079851.34     13872772.03
#Sta/Elev= 30
  2900.8 1306.15  3279.4 1299.68  3359.4 1291.98  3849.6 1277.02  4119.7 1249.14
  4209.7 1225.64  4349.7 1196.85  4439.8 1186.61  4499.8 1174.57  4529.8 1175.01
  4629.8 1196.29  4689.8 1181.99  4859.9 1171.52  4949.9 1155.68  4969.9 1147.88
  4999.4 1137.09  5063.3 1140.09    5080 1148.57    5165 1181.62  5420.1 1197.38
  5570.1 1215.44  5737.1 1221.66  5852.2  1233.4  6046.7  1243.2  6359.1 1255.34
  6556.1 1260.13  6654.6 1262.31  6851.6 1266.46  7040.9 1269.99  7053.6 1269.83
#Mann= 11 ,-1 , 0
  2900.8     .05       0  4969.9     .04       0    5080     .05       0
  5737.1     .07       0  5852.2     .12       0  6046.7     .07       0
  6359.1     .05       0  6556.1     .07       0  6654.6     .05       0
  6851.6     .07       0  7040.9     .05       0
Bank Sta=4969.9,5080
XS Rating Curve= 0 ,0
Exp/Cntr=0.3,0.1

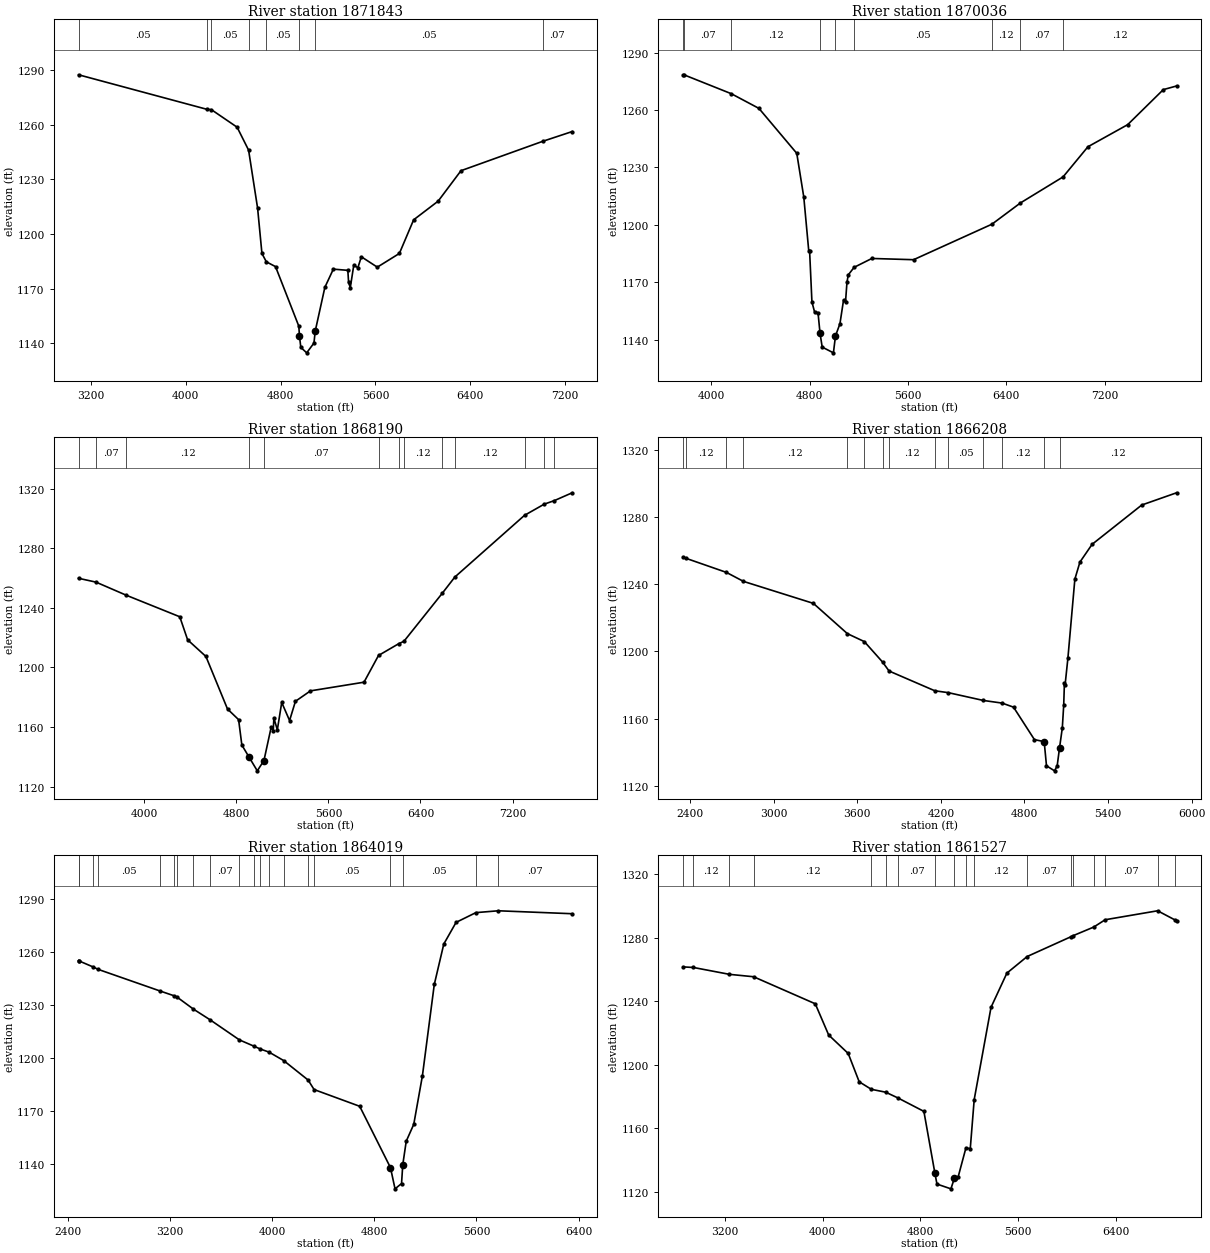
Type RM Length L Ch R = 1 ,1871843 ,1807,1807,1807
BEGIN DESCRIPTION:
Guadalupe River - 79
END DESCRIPTION:
XS GIS Cut Line= 4
      2080493.32     13876324.23      2081520.44     13875361.31
      2081349.25     13874526.76      2080172.75      13873029.4
#Sta/Elev= 30
  3095.6 1287.64  4176.8 1268.66  4216.7 1268.42  4433.3 1258.78  4530.1 1246.16
  4606.1  1214.2  4642.6 1189.29  4679.9 1184.68  4757.3 1182.05  4953.8 1149.25
  4959.1  1143.9  4970.6 1137.59  5020.2 1134.59  5081.6    1140  5091.8 1146.45
  5173.5 1170.66  5244.9 1180.66  5367.2    1180  5373.6 1173.34    5388 1170.47
  5416.9 1182.68  5452.2 1181.49  5481.1 1187.47  5615.8 1181.75  5801.9 1189.29
  5922.2  1207.8  6129.1 1218.09  6321.6 1234.84  7010.1 1250.99  7259.7 1256.39
#Mann= 8 ,-1 , 0
  3095.6     .05       0  4176.8     .07       0  4216.7     .05       0
  4530.1     .07       0  4679.9     .05       0  4959.1     .04       0
  5091.8     .05       0  7010.1     .07       0
Bank Sta=4959.1,5091.8
XS Rating Curve= 0 ,0
Exp/Cntr=0.3,0.1

Type RM Length L Ch R = 1 ,1870036 ,1846,1846,1846
BEGIN DESCRIPTION:
Guadalupe River - 78
END DESCRIPTION:
XS GIS Cut Line= 3
      2083917.08     13875404.09      2083082.55     13874804.94
      2081670.21     13872172.86
#Sta/Elev= 30
  3769.2 1278.35    3777 1278.46  4162.6 1268.56  4387.3 1260.88    4695 1237.38
    4752 1214.53  4792.2 1186.52  4799.2 1186.52  4818.3 1159.63  4840.2 1154.32
  4867.8 1154.04  4884.1 1143.27  4901.8 1136.03    4993 1133.03  5009.9 1141.89
  5046.1 1148.27  5075.7 1160.77  5091.5 1159.74  5103.3 1169.99  5113.9 1173.81
  5161.3 1177.75  5305.5 1182.39  5644.9 1181.74    6282 1200.31  6514.2 1211.44
  6860.4 1225.04  7062.7 1240.81  7385.9 1252.37  7675.8  1270.7  7783.6  1272.6
#Mann= 9 ,-1 , 0
  3769.2     .05       0    3777     .07       0  4162.6     .12       0
  4884.1     .04       0  5009.9     .12       0  5161.3     .05       0
    6282     .12       0  6514.2     .07       0  6860.4     .12       0
Bank Sta=4884.1,5009.9
XS Rating Curve= 0 ,0
Exp/Cntr=0.3,0.1

Type RM Length L Ch R = 1 ,1868190 ,1982,1982,1982
BEGIN DESCRIPTION:
Guadalupe River - 77
END DESCRIPTION:
XS GIS Cut Line= 2
      2084837.23      13874954.7      2082996.95     13871081.56
#Sta/Elev= 30
  3429.6 1259.93  3581.3 1257.35  3845.5 1248.51    4309 1234.08  4377.2 1218.59
  4536.2  1207.4  4723.6 1172.11    4820 1164.96  4848.2 1147.91  4910.9 1139.77
  4982.3 1130.57  5040.2 1137.51  5103.7 1160.13  5120.9 1157.35  5126.4 1166.03
  5156.4 1158.12  5194.6 1176.51  5262.8 1164.37  5313.7 1177.29  5444.3  1184.3
  5909.3 1190.12  6035.3 1208.08  6211.6 1216.01  6256.4 1217.62    6588 1249.75
  6698.6 1260.78  7303.7 1302.23  7475.1 1309.75  7562.6 1312.11  7717.7 1317.38
#Mann= 13 ,-1 , 0
  3429.6     .12       0  3581.3     .07       0  3845.5     .12       0
  4910.9     .04       0  5040.2     .07       0  6035.3     .07       0
  6211.6     .05       0  6256.4     .12       0    6588     .05       0
  6698.6     .12       0  7303.7     .07       0  7475.1     .12       0
  7562.6     .07       0
Bank Sta=4910.9,5040.2
XS Rating Curve= 0 ,0
Exp/Cntr=0.3,0.1

Type RM Length L Ch R = 1 ,1866208 ,2189,2189,2189
BEGIN DESCRIPTION:
Guadalupe River - 76
END DESCRIPTION:
XS GIS Cut Line= 4
      2085008.44     13874847.73      2085650.39     13873970.39
       2085586.2      13872215.7      2085949.96     13871616.56
#Sta/Elev= 30
  2347.9  1255.9  2366.9 1255.48  2659.9 1247.02  2782.3 1241.67  3284.4 1228.58
  3528.5 1210.57  3650.3 1205.83  3780.7  1193.7  3827.8 1188.33  4155.8 1176.58
  4254.4 1175.43  4504.6 1170.81  4639.5 1169.24  4721.3 1166.82  4871.4  1147.5
  4941.4 1146.31  4957.9 1131.93  5015.6 1128.93  5034.7 1131.93  5051.5 1142.56
  5071.5 1154.45  5081.5 1167.92  5086.7 1181.31  5091.7 1180.26  5111.5 1195.85
  5161.6 1243.01  5197.9 1253.14  5285.3 1263.71  5641.7  1287.1  5891.8 1294.39
#Mann= 14 ,-1 , 0
  2347.9     .07       0  2366.9     .12       0  2659.9     .05       0
  2782.3     .12       0  3528.5     .07       0  3650.3     .12       0
  3780.7     .05       0  3827.8     .12       0  4155.8     .07       0
  4254.4     .05       0  4504.6     .07       0  4639.5     .12       0
  4941.4     .04       0  5051.5     .12       0
Bank Sta=4941.4,5051.5
XS Rating Curve= 0 ,0
Exp/Cntr=0.3,0.1

Type RM Length L Ch R = 1 ,1864019 ,2492,2492,2492
BEGIN DESCRIPTION:
Guadalupe River - 75
END DESCRIPTION:
XS GIS Cut Line= 3
      2085179.61     13874911.95      2085949.98     13874269.97
      2088431.15     13872836.88
#Sta/Elev= 30
  2482.3 1255.32    2487 1255.06  2592.8 1251.79  2635.2 1250.32  3119.5 1238.08
    3228  1235.4  3251.1 1234.75  3382.8 1227.75  3513.2 1221.71  3742.7 1210.33
  3858.6  1206.7    3908 1205.11  3974.4 1203.42  4090.3 1198.58  4281.5 1187.55
  4327.9 1182.18  4685.4 1172.69  4926.6  1137.9  4962.3  1125.9  5013.3  1128.9
  5022.8 1139.53  5050.1 1152.92    5109 1162.46  5176.9 1190.03  5269.8 1241.73
  5344.4 1264.68  5440.6 1276.94  5595.8 1282.46  5771.6 1283.51  6350.4 1281.84
#Mann= 20 ,-1 , 0
  2482.3     .07       0    2487     .05       0  2592.8     .07       0
  2635.2     .05       0  3119.5     .12       0    3228     .05       0
  3251.1     .12       0  3382.8     .12       0  3513.2     .07       0
  3742.7     .05       0  3858.6     .07       0    3908     .05       0
  3974.4     .07       0  4090.3     .12       0  4281.5     .07       0
  4327.9     .05       0  4926.6     .04       0  5022.8     .05       0
  5595.8     .05       0  5771.6     .07       0
Bank Sta=4926.6,5022.8
XS Rating Curve= 0 ,0
Exp/Cntr=0.3,0.1

Type RM Length L Ch R = 1 ,1861527 ,1834,1834,1834
BEGIN DESCRIPTION:
Guadalupe River - 74
END DESCRIPTION:
XS GIS Cut Line= 2
      2085350.81     13875660.89      2089395.19     13875553.89
#Sta/Elev= 30
  2854.1 1261.62  2939.6 1261.26  3235.6 1256.93    3433 1255.42  3938.7  1238.4
  4048.7 1218.74  4208.8 1207.12  4298.8 1189.29  4398.4 1184.56  4515.9 1182.75
  4616.9 1179.11    4829 1170.67    4919 1131.84  4936.1 1124.92  5050.6 1121.92
  5079.1 1128.67  5109.1 1129.24  5173.1 1147.58  5209.1 1147.27  5241.3  1178.1
  5379.2 1236.18  5509.2  1257.7  5675.6 1268.16  6036.4 1280.68  6050.1  1281.2
  6221.2  1286.7  6314.9  1291.3  6744.6 1296.94  6886.2  1291.2  6899.9 1290.71
#Mann= 18 ,-1 , 0
  2854.1     .05       0  2939.6     .12       0  3235.6     .07       0
    3433     .12       0  4398.4     .07       0  4515.9     .12       0
  4616.9     .07       0    4919     .04       0  5079.1     .07       0
  5173.1     .05       0  5241.3     .12       0  5675.6     .07       0
  6036.4     .12       0  6050.1     .07       0  6221.2     .12       0
  6314.9     .07       0  6744.6     .05       0  6886.2     .07       0
Bank Sta=4919,5079.1
XS Rating Curve= 0 ,0
Exp/Cntr=0.3,0.1

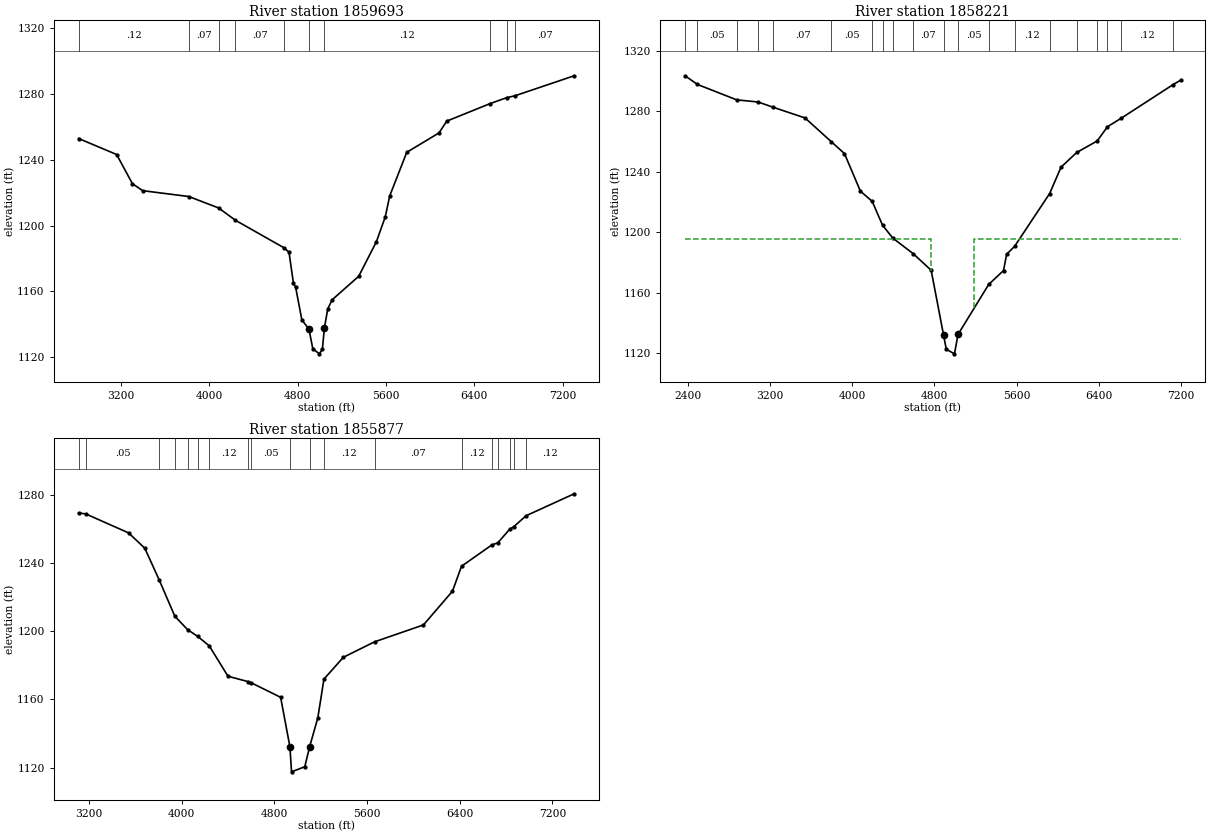
Type RM Length L Ch R = 1 ,1859693 ,1472,1472,1472
BEGIN DESCRIPTION:
Guadalupe River - 73
END DESCRIPTION:
XS GIS Cut Line= 4
      2085949.97     13875746.47      2087084.11      13877201.6
      2088068.45      13877137.4      2089352.37     13876088.87
#Sta/Elev= 30
  2816.2 1252.98  3160.4 1243.25  3303.4 1225.52  3396.5 1221.26  3813.9 1217.71
  4083.9 1210.76  4236.5 1203.26  4677.8 1186.47  4722.1 1183.77  4762.2 1164.91
  4782.2 1162.47  4838.3 1142.67  4902.5 1137.09  4937.9 1125.02  4997.8 1122.02
  5024.4 1125.02  5042.8  1137.9  5072.9 1149.35  5112.9 1154.92  5353.5  1169.2
  5513.8 1190.25    5594 1205.34  5634.1 1218.05  5788.6 1244.59  6080.8  1256.4
  6151.2 1263.57  6539.3  1274.1  6692.5 1277.81  6768.6 1278.97  7305.2 1291.14
#Mann= 10 ,-1 , 0
  2816.2     .12       0  3813.9     .07       0  4083.9     .12       0
  4236.5     .07       0  4677.8     .12       0  4902.5     .04       0
  5042.8     .12       0  6539.3     .07       0  6692.5     .12       0
  6768.6     .07       0
Bank Sta=4902.5,5042.8
XS Rating Curve= 0 ,0
Exp/Cntr=0.3,0.1

Type RM Length L Ch R = 1 ,1858221 ,2344,2344,2344
BEGIN DESCRIPTION:
Guadalupe River - 72
END DESCRIPTION:
XS GIS Cut Line= 3
      2085115.45     13878335.73      2086656.13     13878528.32
      2089908.74     13878143.14
#Sta/Elev= 30
    2371 1303.45  2491.5 1297.72  2873.8 1287.54  3081.2 1286.14  3231.3 1282.61
  3539.6 1275.59  3797.3 1259.79  3923.7 1252.05    4079 1227.24  4193.9  1220.5
  4294.5 1204.75  4394.1 1196.25  4593.3 1185.92  4768.4 1174.97  4889.2 1132.15
  4915.7 1122.76  4995.6 1119.76  5030.2 1132.57  5329.5 1165.66  5473.3 1174.76
  5503.5 1185.51    5582 1190.84  5922.7 1225.65  6033.7 1243.08  6186.9 1252.79
  6386.1 1260.39  6485.7 1269.76    6619 1275.36  7124.5 1297.58    7199 1300.54
#Mann= 20 ,-1 , 0
    2371     .05       0  2491.5     .05       0  2873.8     .07       0
  3081.2     .05       0  3231.3     .07       0  3797.3     .05       0
  4193.9     .05       0  4294.5     .07       0  4394.1     .12       0
  4593.3     .07       0  4889.2     .04       0  5030.2     .05       0
  5329.5     .07       0    5582     .12       0  5922.7     .07       0
  6186.9     .12       0  6386.1     .07       0  6485.7     .05       0
    6619     .12       0  7124.5     .07       0
#XS Ineff= 2 , 0
       0 4769.23  1195.7 5186.81       0 1195.44
Permanent Ineff=
       F       F
Bank Sta=4889.2,5030.2
XS Rating Curve= 0 ,0
Exp/Cntr=0.3,0.1

Type RM Length L Ch R = 1 ,1855877 ,2210,2210,2210
BEGIN DESCRIPTION:
Guadalupe River - 71
END DESCRIPTION:
XS GIS Cut Line= 3
       2086335.2      13880411.4      2089651.95     13880176.02
      2090336.73     13879512.64
#Sta/Elev= 30
  3108.9 1269.51  3170.9 1268.92  3539.8 1257.81  3680.1  1248.8  3803.7  1230.3
  3939.5 1208.85  4049.4 1201.01  4137.6 1196.97  4236.6 1191.47  4398.5 1173.61
    4569 1170.52  4600.7 1169.73  4853.1 1161.24  4933.3  1132.1  4947.1 1117.49
  5061.7 1120.49  5102.5 1132.06  5173.9 1149.13  5226.8 1171.93  5394.4 1184.74
  5663.9 1193.83  6086.2 1203.76  6336.8 1223.58  6414.9 1238.22  6676.9 1250.74
  6727.4 1251.93  6831.1 1259.97  6864.4 1261.37  6972.6 1267.88  7387.4 1280.76
#Mann= 19 ,-1 , 0
  3108.9     .07       0  3170.9     .05       0  3803.7     .07       0
  3939.5     .12       0  4049.4     .05       0  4137.6     .07       0
  4236.6     .12       0    4569     .07       0  4600.7     .05       0
  4933.3     .04       0  5102.5     .05       0  5226.8     .12       0
  5663.9     .07       0  6414.9     .12       0  6676.9     .07       0
  6727.4     .12       0  6831.1     .05       0  6864.4     .07       0
  6972.6     .12       0
Bank Sta=4933.3,5102.5
XS Rating Curve= 0 ,0
Exp/Cntr=0.3,0.1