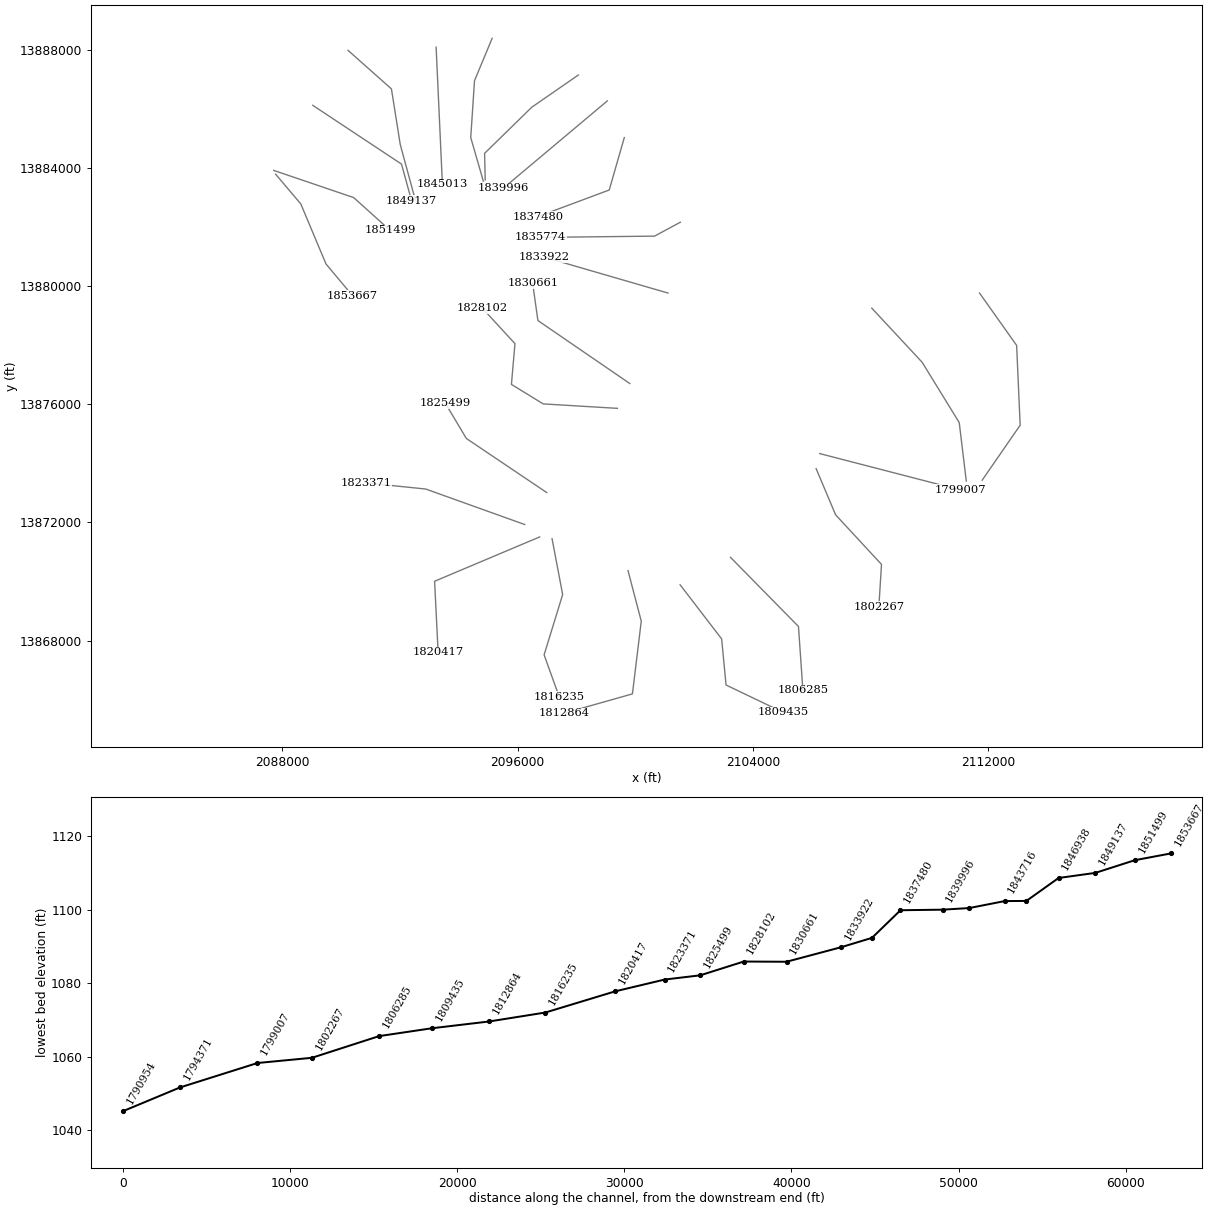
HEC-RAS study Guadalupe River.prj: Guadalupe River Base Level Engineering

--- Guadalupe River.g01 (geometry) --- (continued)

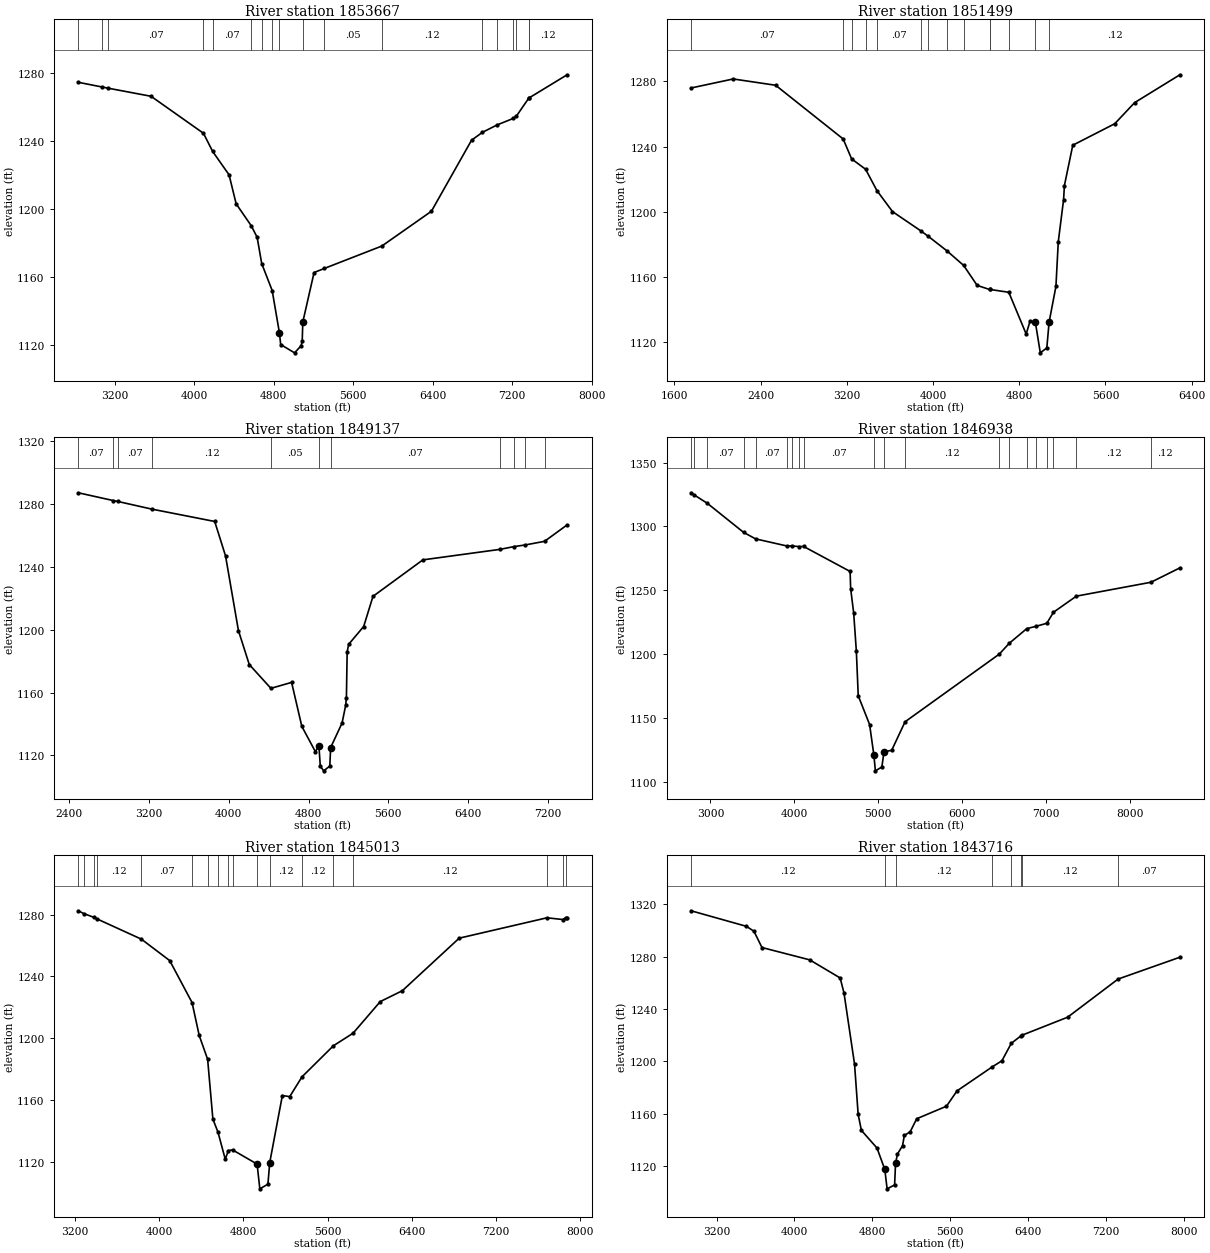
Type RM Length L Ch R = 1 ,1853667 ,2168,2168,2168
BEGIN DESCRIPTION:
Guadalupe River - 70
END DESCRIPTION:
XS GIS Cut Line= 4
      2087768.86     13883792.41      2088624.82     13882786.66
      2089480.76     13880753.78      2090379.49     13879683.87
#Sta/Elev= 30
  2830.4 1274.63  3067.8 1271.89  3130.4 1271.17  3563.1 1266.41  4091.3 1244.62
  4184.1 1233.91  4349.2 1220.16  4420.4  1203.1  4572.6  1190.2    4632 1183.37
    4678 1167.92  4783.3 1152.08  4856.5  1127.1    4869 1120.27  5008.9 1115.39
  5075.1 1119.59    5086 1122.42  5091.8 1133.52  5205.4 1162.67  5310.2  1165.1
  5888.2 1178.26  6387.3 1198.72  6791.8 1240.56  6901.9 1245.21  7050.9 1249.59
    7210 1253.33    7242  1254.6  7367.2 1265.24  7369.1 1265.37  7754.1 1279.06
#Mann= 18 ,-1 , 0
  2830.4     .07       0  3067.8     .12       0  3130.4     .07       0
  4091.3     .12       0  4184.1     .07       0  4572.6     .05       0
    4678     .12       0  4783.3     .07       0  4856.5     .04       0
  5091.8     .12       0  5310.2     .05       0  5888.2     .12       0
  6901.9     .07       0  7050.9     .05       0    7210     .12       0
    7242     .05       0  7367.2     .07       0  7369.1     .12       0
Bank Sta=4856.5,5091.8
XS Rating Curve= 0 ,0
Exp/Cntr=0.3,0.1

Type RM Length L Ch R = 1 ,1851499 ,2362,2362,2362
BEGIN DESCRIPTION:
Guadalupe River - 69
END DESCRIPTION:
XS GIS Cut Line= 3
      2087704.71     13883920.78      2090422.31     13883000.65
      2091662.28     13881888.95
#Sta/Elev= 30
  1755.9 1275.95  2146.8 1281.48  2540.3 1277.62  3166.7 1244.69  3245.2 1232.47
  3374.4 1226.14  3479.6 1213.07  3624.4 1200.15  3887.8 1188.31  3953.9  1185.1
  4130.3 1176.04  4284.3 1167.14  4410.1 1154.88  4524.7 1152.39  4529.8 1152.39
  4703.1 1150.68  4864.7 1125.05  4899.8 1132.86  4949.9 1132.24  4995.6 1113.54
    5056 1116.57    5077 1132.27  5140.5 1154.25  5162.2 1181.59  5211.6  1207.5
  5219.1  1216.1  5296.8 1240.85  5686.3 1254.04  5870.2 1266.95  6290.4 1284.05
#Mann= 14 ,-1 , 0
  1755.9     .07       0  3166.7     .05       0  3245.2     .07       0
  3374.4     .12       0  3479.6     .07       0  3887.8     .05       0
  3953.9     .12       0  4130.3     .07       0  4284.3     .12       0
  4524.7     .07       0  4529.8     .05       0  4703.1     .07       0
  4949.9     .04       0    5077     .12       0
Bank Sta=4949.9,5077
XS Rating Curve= 0 ,0
Exp/Cntr=0.3,0.1

Type RM Length L Ch R = 1 ,1849137 ,2199,2199,2199
BEGIN DESCRIPTION:
Guadalupe River - 68
END DESCRIPTION:
XS GIS Cut Line= 3
      2089031.35     13886124.88      2092048.61     13884134.78
       2092390.5     13882895.44
#Sta/Elev= 30
  2492.1 1287.25  2839.9 1282.33  2885.4 1281.76  3231.5 1276.81  3859.6 1268.97
    3968 1247.07  4097.5 1199.44  4205.9 1177.84    4423 1162.65  4630.4 1166.44
  4732.8 1138.43  4868.4 1122.35  4904.3 1125.91    4918 1113.09  4951.8 1110.09
  5013.3 1113.09  5021.8 1124.91  5136.2 1140.54  5172.3 1151.72  5179.8 1156.73
  5187.4 1185.87  5202.5 1190.71    5353 1202.05  5446.3 1221.26  5946.2  1244.5
  6721.5 1251.22  6859.8 1252.96  6967.3 1253.95  7165.9 1256.31  7392.2 1266.78
#Mann= 11 ,-1 , 0
  2492.1     .07       0  2839.9     .05       0  2885.4     .07       0
  3231.5     .12       0    4423     .05       0  4904.3     .04       0
  5021.8     .07       0  6721.5     .07       0  6859.8     .12       0
  6967.3     .07       0  7165.9     .12       0
Bank Sta=4904.3,5021.8
XS Rating Curve= 0 ,0
Exp/Cntr=0.3,0.1

Type RM Length L Ch R = 1 ,1846938 ,1925,1925,1925
BEGIN DESCRIPTION:
Guadalupe River - 67
END DESCRIPTION:
XS GIS Cut Line= 4
      2090229.69     13887986.57      2091706.23     13886681.23
      2092005.81     13884798.14      2092519.37     13882915.09
#Sta/Elev= 30
  2769.7 1326.38  2803.1 1324.84  2964.5 1318.09  3395.1 1295.43  3538.6  1290.3
  3919.1 1284.63  3969.2 1284.79  4054.3 1284.27  4112.8 1284.33  4666.2 1264.79
  4672.8 1251.34  4708.8 1232.27  4740.5 1202.65  4763.3 1167.48  4898.7 1144.97
  4949.3  1121.2  4967.9  1108.7  5044.7  1111.7  5070.8 1123.61    5162 1124.75
  5321.8 1147.11  6445.1 1200.06  6564.9 1208.59    6773 1220.02    6889 1221.94
  7012.5 1224.23  7091.2 1232.83  7364.6 1245.46    8254 1256.33  8599.1 1267.58
#Mann= 20 ,-1 , 0
  2769.7     .07       0  2803.1     .05       0  2964.5     .07       0
  3395.1     .07       0  3538.6     .07       0  3919.1     .05       0
  3969.2     .07       0  4054.3     .05       0  4112.8     .07       0
  4949.3     .04       0  5070.8     .12       0  5321.8     .12       0
  6445.1     .07       0  6564.9     .12       0    6773     .05       0
    6889     .07       0  7012.5     .05       0  7091.2     .12       0
  7364.6     .12       0    8254     .12       0
Bank Sta=4949.3,5070.8
XS Rating Curve= 0 ,0
Exp/Cntr=0.3,0.1

Type RM Length L Ch R = 1 ,1845013 ,1297,1297,1297
BEGIN DESCRIPTION:
Guadalupe River - 66
END DESCRIPTION:
XS GIS Cut Line= 2
      2093225.54     13888093.55      2093439.53     13883449.98
#Sta/Elev= 30
  3229.4 1282.41  3281.7  1280.6    3376  1278.2  3409.1 1277.09  3829.2 1264.05
  4098.9 1250.16  4311.3 1223.01  4379.2 1201.71  4459.4 1186.29  4509.3 1147.61
  4557.8 1139.14  4627.1 1121.61  4656.1 1127.19    4696 1127.69  4929.8 1118.46
  4955.7 1102.46  5032.7 1105.46  5049.9 1119.44    5170 1162.84  5240.1 1162.14
  5356.6 1174.93  5655.3 1195.04  5842.8 1203.19    6101 1223.64  6311.2 1230.68
  6851.8 1264.68  7686.5 1277.87  7838.7 1276.73  7865.2 1278.04  7877.9 1277.96
#Mann= 18 ,-1 , 0
  3229.4     .07       0  3281.7     .12       0    3376     .07       0
  3409.1     .12       0  3829.2     .07       0  4311.3     .05       0
  4459.4     .12       0  4557.8     .05       0  4656.1     .07       0
    4696     .05       0  4929.8     .04       0  5049.9     .12       0
  5356.6     .12       0  5655.3     .07       0  5842.8     .12       0
  7686.5     .07       0  7838.7     .12       0  7865.2     .07       0
Bank Sta=4929.8,5049.9
XS Rating Curve= 0 ,0
Exp/Cntr=0.3,0.1

Type RM Length L Ch R = 1 ,1843716 ,2124,2124,2124
BEGIN DESCRIPTION:
Guadalupe River - 65
END DESCRIPTION:
XS GIS Cut Line= 4
      2095130.02     13888393.12      2094530.86     13886959.41
      2094402.47     13885033.53       2094829.8     13883559.24
#Sta/Elev= 30
  2938.4 1315.13  3507.2 1303.22    3584 1299.46  3666.3 1287.02  4156.5 1277.59
  4469.3 1263.72  4508.5 1252.28    4617 1197.72  4653.8 1159.46  4687.1 1147.14
  4847.5 1133.64  4927.6 1117.23  4951.3 1102.42  5028.3 1105.42  5037.9 1122.07
  5057.9 1129.08  5109.8 1135.44  5128.1 1143.24  5188.2 1146.04  5255.1 1156.04
  5560.8 1165.63  5669.3 1177.36  6030.6 1195.72  6130.3 1200.39  6226.4 1213.74
  6327.4 1219.56  6337.4 1219.97  6804.8 1233.71    7323  1262.9  7957.4 1279.59
#Mann= 8 ,-1 , 0
  2938.4     .12       0  4927.6     .04       0  5037.9     .12       0
  6030.6     .07       0  6226.4     .12       0  6327.4     .07       0
  6337.4     .12       0    7323     .07       0
Bank Sta=4927.6,5037.9
XS Rating Curve= 0 ,0
Exp/Cntr=0.3,0.1

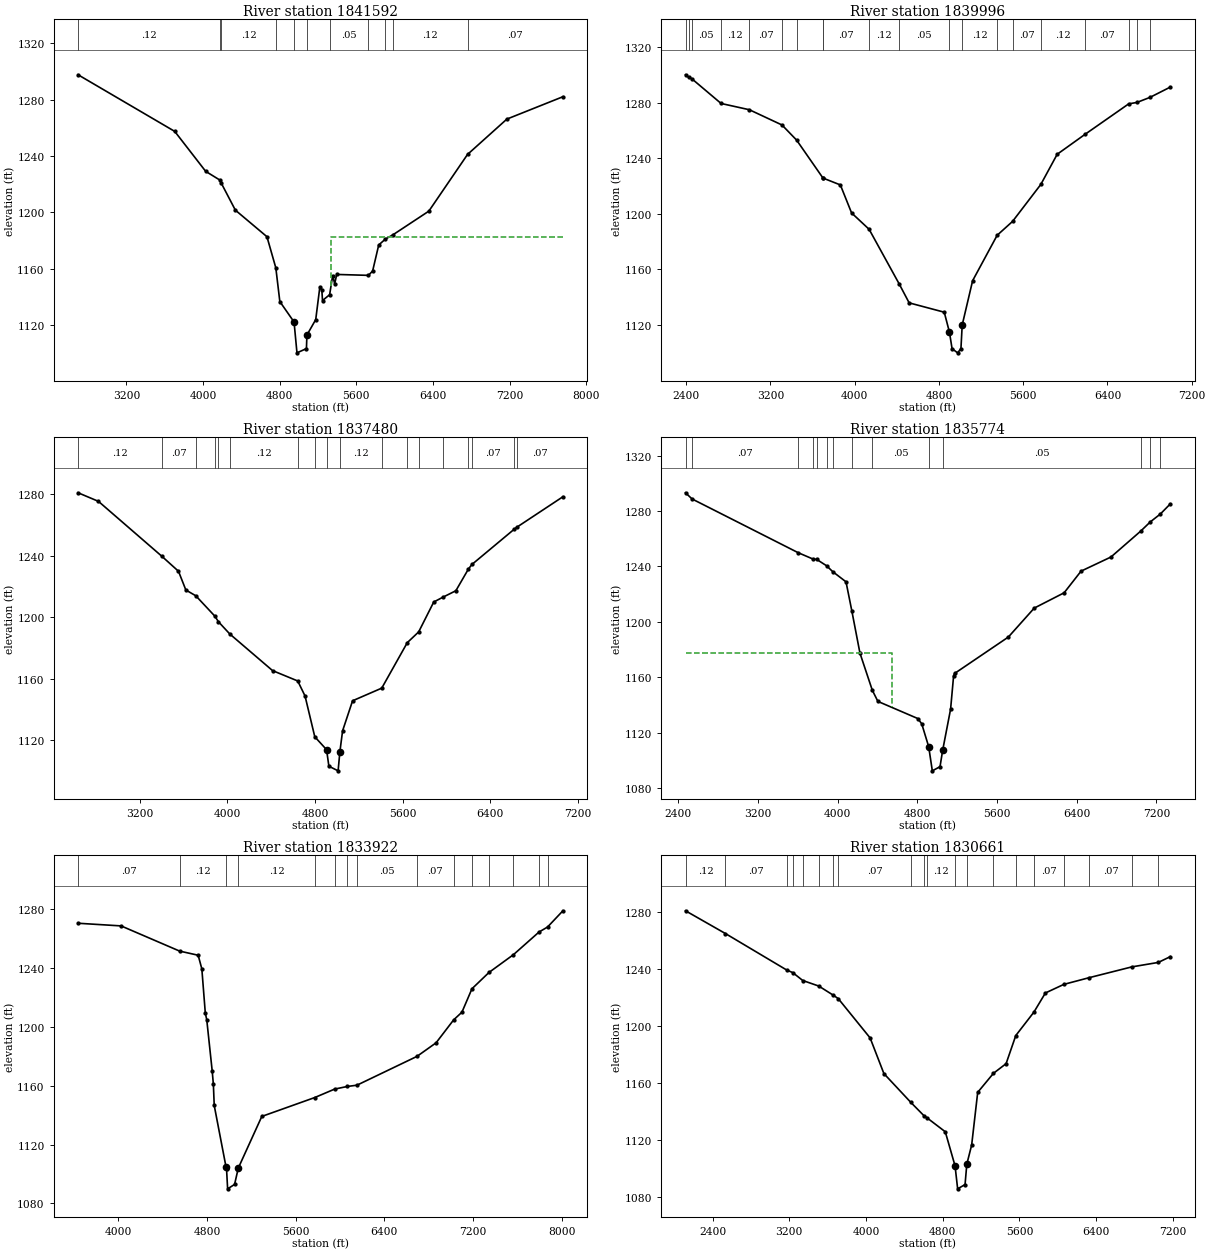
Type RM Length L Ch R = 1 ,1841592 ,1596,1596,1596
BEGIN DESCRIPTION:
Guadalupe River - 64
END DESCRIPTION:
XS GIS Cut Line= 4
      2098061.65       13887152.      2096478.14     13886060.66
      2094873.24     13884498.56      2094894.64     13883599.88
#Sta/Elev= 30
  2695.8 1297.54  3704.8 1257.42  4027.7 1229.13  4177.5 1222.87  4191.2 1220.68
  4337.8 1201.62  4667.5  1182.8  4760.2 1160.72    4802 1136.87  4950.5 1122.37
  4980.9 1100.52  5079.8 1103.52  5084.8 1113.12  5176.8 1124.08  5219.2 1146.91
  5240.4 1145.17  5247.5 1137.56  5321.9 1141.71  5353.5 1155.26  5374.8 1149.48
    5396 1156.07    5727 1155.42  5770.7 1158.48  5834.5 1176.95  5904.4 1181.15
  5980.1 1184.02  6357.7 1200.92  6761.8 1241.11  7172.2 1266.13  7757.5 1281.99
#Mann= 11 ,-1 , 0
  2695.8     .12       0  4177.5     .07       0  4191.2     .12       0
  4760.2     .05       0  4950.5     .04       0  5084.8     .07       0
  5321.9     .05       0    5727     .12       0  5904.4     .07       0
  5980.1     .12       0  6761.8     .07       0
#XS Ineff= 2 , 0
       0                 5336.26       0 1182.37
Permanent Ineff=
       F       F
Bank Sta=4950.5,5084.8
XS Rating Curve= 0 ,0
Exp/Cntr=0.3,0.1

Type RM Length L Ch R = 1 ,1839996 ,2516,2516,2516
BEGIN DESCRIPTION:
Guadalupe River - 63
END DESCRIPTION:
XS GIS Cut Line= 2
        2099046.     13886274.66      2095515.22     13883321.64
#Sta/Elev= 30
  2393.9 1299.94  2425.7 1298.06  2451.9 1297.21  2731.7 1279.32  3000.3 1274.81
  3309.8 1263.86  3448.6    1253  3699.1  1225.7  3699.2  1225.7  3864.1 1220.77
  3970.8 1200.62  4137.1 1188.88  4422.6 1149.61  4517.3    1136  4850.5 1129.28
  4899.9 1114.91  4924.6 1103.08  4977.2 1100.08  5008.9 1103.08  5020.9 1120.09
  5119.8 1151.94  5352.8 1184.58    5499 1194.55    5767 1221.09  5922.7  1242.8
  6188.9 1257.23  6601.5 1279.03  6679.7 1280.06  6803.5 1283.69  6996.8  1291.1
#Mann= 20 ,-1 , 0
  2393.9     .05       0  2425.7     .12       0  2451.9     .05       0
  2731.7     .12       0  3000.3     .07       0  3309.8     .05       0
  3448.6     .07       0  3699.1     .12       0  3699.2     .07       0
  4137.1     .12       0  4422.6     .05       0  4899.9     .04       0
  5020.9     .12       0  5352.8     .05       0    5499     .07       0
    5767     .12       0  6188.9     .07       0  6601.5     .12       0
  6679.7     .07       0  6803.5     .12       0
Bank Sta=4899.9,5020.9
XS Rating Curve= 0 ,0
Exp/Cntr=0.3,0.1

Type RM Length L Ch R = 1 ,1837480 ,1706,1706,1706
BEGIN DESCRIPTION:
Guadalupe River - 62
END DESCRIPTION:
XS GIS Cut Line= 3
      2099623.75     13885033.52      2099110.19     13883257.43
      2096693.94     13882359.36
#Sta/Elev= 30
    2637 1280.84  2822.8 1275.26  3401.9 1239.52  3553.6 1229.78  3620.8 1217.59
  3711.8 1213.82  3885.8 1200.56  3918.5 1196.92  4021.8 1188.98  4412.4 1165.15
  4642.4  1158.4  4709.1 1148.62  4798.1 1122.08  4905.6  1113.7  4926.8 1102.93
  5011.1 1099.93    5027 1112.25    5052 1125.98  5143.1 1145.51  5409.5 1153.74
  5642.7 1183.33  5746.6 1190.33  5884.3 1209.78  5966.9 1212.87  6086.1  1217.1
  6200.5 1231.19  6232.5 1234.18  6615.9 1256.95  6647.2 1258.64  7063.6 1278.26
#Mann= 18 ,-1 , 0
    2637     .12       0  3401.9     .07       0  3711.8     .05       0
  3885.8     .07       0  3918.5     .05       0  4021.8     .12       0
  4642.4     .05       0  4798.1     .12       0  4905.6     .04       0
    5027     .12       0  5409.5     .12       0  5642.7     .05       0
  5746.6     .12       0  5966.9     .07       0  6200.5     .12       0
  6232.5     .07       0  6615.9     .05       0  6647.2     .07       0
Bank Sta=4905.6,5027
XS Rating Curve= 0 ,0
Exp/Cntr=0.3,0.1

Type RM Length L Ch R = 1 ,1835774 ,1852,1852,1852
BEGIN DESCRIPTION:
Guadalupe River - 61
END DESCRIPTION:
XS GIS Cut Line= 3
      2101528.25      13882166.1      2100650.89     13881695.33
      2096778.91     13881652.54
#Sta/Elev= 30
  2472.2 1293.21  2538.3 1288.74  3602.1 1249.99  3749.8 1245.43  3790.4 1245.06
  3888.9 1240.49  3950.7 1236.24  4083.8 1228.91  4141.5 1208.19  4223.8 1177.41
  4347.8 1150.62  4403.8 1142.56  4803.9  1130.2  4843.9 1126.41  4913.9 1109.86
  4950.4 1092.41  5027.7 1095.41  5053.9 1107.11  5133.9 1136.98  5163.9 1160.81
  5173.9 1162.73  5713.9 1189.03  5973.9 1209.94  6273.9 1220.99    6444 1236.63
    6744 1246.82  7041.7 1265.46  7140.2 1272.25  7238.8 1277.79  7340.1 1285.19
#Mann= 14 ,-1 , 0
  2472.2     .05       0  2538.3     .07       0  3602.1     .12       0
  3749.8     .07       0  3790.4     .12       0  3888.9     .07       0
  3950.7     .12       0  4141.5     .07       0  4347.8     .05       0
  4913.9     .04       0  5053.9     .05       0  7041.7     .07       0
  7140.2     .12       0  7238.8     .05       0
#XS Ineff= 2 , 0
       0 4540.66 1177.33               0
Permanent Ineff=
       F       F
Bank Sta=4913.9,5053.9
XS Rating Curve= 0 ,0
Exp/Cntr=0.3,0.1

Type RM Length L Ch R = 1 ,1833922 ,3261,3261,3261
BEGIN DESCRIPTION:
Guadalupe River - 60
END DESCRIPTION:
XS GIS Cut Line= 2
      2101107.34     13879768.13      2096905.97      13880983.4
#Sta/Elev= 30
  3636.7  1270.6  4024.3  1268.8  4552.7 1251.65  4719.8 1248.83    4753 1239.56
  4784.2 1209.53  4797.5 1204.85  4846.7  1169.9  4857.1 1160.96  4864.7 1146.62
  4970.7 1104.94  4975.9 1103.38  4985.6 1089.86  5048.3 1092.86  5081.9    1104
    5294 1139.14  5771.6 1151.99    5951 1157.74  6064.2 1159.51  6152.4  1160.4
  6694.3 1180.02  6866.2 1189.24  7024.3 1204.82  7099.4 1210.09  7189.8 1226.02
  7343.3 1237.11  7564.4 1249.25  7794.9 1264.64  7871.9 1268.05  8010.3 1279.09
#Mann= 15 ,-1 , 0
  3636.7     .07       0  4552.7     .12       0  4970.7     .04       0
  5081.9     .12       0  5771.6     .07       0    5951     .05       0
  6064.2     .07       0  6152.4     .05       0  6694.3     .07       0
  7024.3     .05       0  7189.8     .12       0  7343.3     .07       0
  7564.4     .12       0  7794.9     .07       0  7871.9     .12       0
Bank Sta=4970.7,5081.9
XS Rating Curve= 0 ,0
Exp/Cntr=0.3,0.1

Type RM Length L Ch R = 1 ,1830661 ,2559,2559,2559
BEGIN DESCRIPTION:
Guadalupe River - 59
END DESCRIPTION:
XS GIS Cut Line= 3
      2099809.39     13876704.39      2096686.63     13878836.28
      2096506.47     13880097.39
#Sta/Elev= 30
  2118.2 1280.56  2534.3 1264.63  3173.8 1239.07  3236.5 1237.28  3340.8 1231.75
  3507.8 1227.86  3661.1 1221.38  3711.1 1219.05  4043.1 1191.55  4186.7  1166.6
  4467.4 1146.44  4604.4  1137.1  4634.7 1135.69  4826.8 1125.86  4928.5 1102.04
  4955.7 1085.91    5033 1088.91  5051.1 1103.12  5101.9 1116.62  5164.8 1153.46
  5329.1 1166.78  5460.9 1173.55  5561.9 1193.21  5751.2 1209.65  5870.7 1223.02
  6063.5 1229.05  6328.7 1233.76  6772.4 1241.29  7047.8  1244.4  7173.2 1248.46
#Mann= 20 ,-1 , 0
  2118.2     .12       0  2534.3     .07       0  3173.8     .05       0
  3236.5     .07       0  3340.8     .05       0  3507.8     .07       0
  3661.1     .05       0  3711.1     .07       0  4467.4     .12       0
  4604.4     .07       0  4634.7     .12       0  4928.5     .04       0
  5051.1     .12       0  5329.1     .07       0  5561.9     .05       0
  5751.2     .07       0  6063.5     .12       0  6328.7     .07       0
  6772.4     .05       0  7047.8     .07       0
Bank Sta=4928.5,5051.1
XS Rating Curve= 0 ,0
Exp/Cntr=0.3,0.1

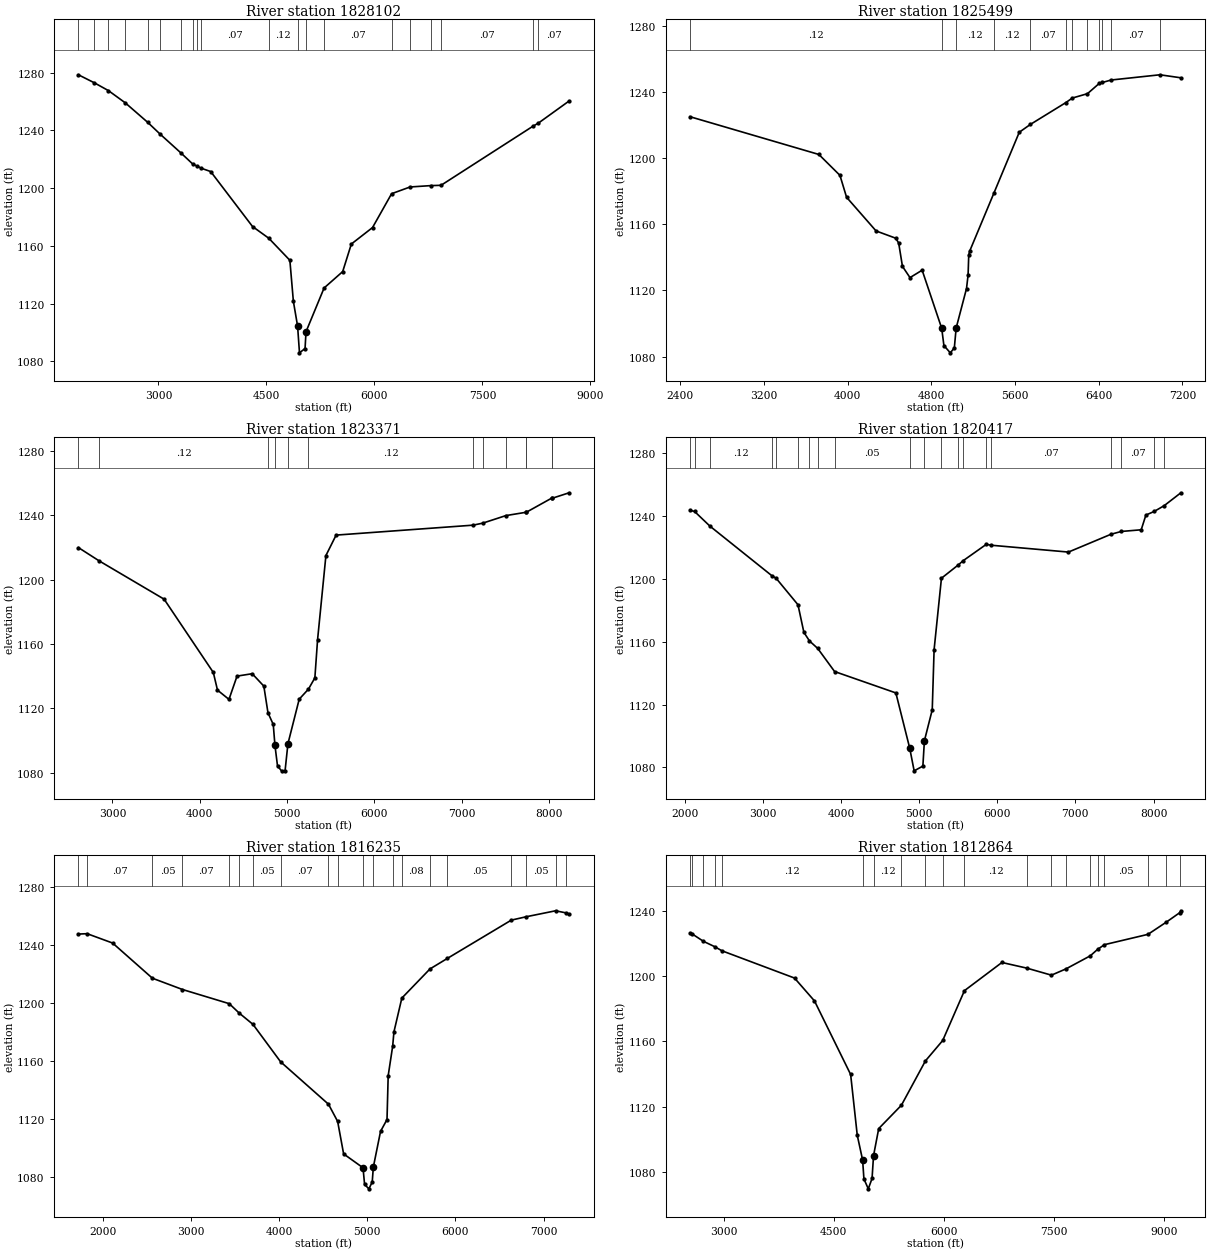
Type RM Length L Ch R = 1 ,1828102 ,2603,2603,2603
BEGIN DESCRIPTION:
Guadalupe River - 58
END DESCRIPTION:
XS GIS Cut Line= 5
      2099389.08     13875863.61      2096866.79     13876013.74
      2095785.82     13876674.34      2095905.93     13878055.58
      2094794.91     13879256.68
#Sta/Elev= 30
  1887.5 1278.55  2110.2 1272.96  2305.5 1267.56    2539  1259.1  2847.5 1245.73
  3022.3 1237.47  3309.1 1224.53    3478 1216.63  3540.2 1215.21  3595.2 1213.79
  3724.8 1211.54  4305.9 1173.47  4531.5 1165.36  4824.8 1150.06  4873.4 1121.67
    4932 1104.51  4958.3 1085.97  5035.7 1088.97  5049.2 1100.61  5300.2 1130.89
  5558.4 1142.24  5678.6 1161.33  5972.9 1172.74  6237.8 1196.18  6494.6 1200.85
  6786.6  1201.8  6924.2 1201.99  8199.5 1242.87  8276.6 1245.08  8703.7 1260.41
#Mann= 20 ,-1 , 0
  1887.5     .12       0  2110.2     .07       0  2305.5     .12       0
    2539     .07       0  2847.5     .12       0  3022.3     .07       0
  3309.1     .12       0    3478     .07       0  3540.2     .12       0
  3595.2     .07       0  4531.5     .12       0    4932     .04       0
  5049.2     .12       0  5300.2     .07       0  6237.8     .12       0
  6494.6     .07       0  6786.6     .05       0  6924.2     .07       0
  8199.5     .05       0  8276.6     .07       0
Bank Sta=4932,5049.2
XS Rating Curve= 0 ,0
Exp/Cntr=0.3,0.1

Type RM Length L Ch R = 1 ,1825499 ,2128,2128,2128
BEGIN DESCRIPTION:
Guadalupe River - 57
END DESCRIPTION:
XS GIS Cut Line= 3
      2096986.86     13873011.07      2094254.44     13874842.69
       2093533.8     13876043.76
#Sta/Elev= 30
  2494.5 1224.98  3724.7 1202.18  3926.3 1189.54  3989.6  1176.3  4271.5 1155.93
  4459.1 1151.55  4487.6 1148.63  4523.7 1134.52  4595.7 1127.71  4711.9  1132.2
  4898.8 1097.07  4919.9 1086.64  4980.9 1082.22  5019.6 1085.22  5036.9  1097.2
    5136 1121.12    5151 1129.26  5157.3 1141.39    5166 1143.69  5398.4 1178.91
  5640.2 1215.61  5747.1 1220.37  6083.3 1233.46  6147.2 1236.29  6292.2 1238.94
  6404.9 1245.16  6435.2 1245.71  6517.5 1247.19  6984.5 1250.36  7184.7 1248.53
#Mann= 12 ,-1 , 0
  2494.5     .12       0  4898.8     .04       0  5036.9     .12       0
  5398.4     .12       0  5747.1     .07       0  6083.3     .12       0
  6147.2     .07       0  6292.2     .05       0  6404.9     .07       0
  6435.2     .05       0  6517.5     .07       0  6984.5     .12       0
Bank Sta=4898.8,5036.9
XS Rating Curve= 0 ,0
Exp/Cntr=0.3,0.1

Type RM Length L Ch R = 1 ,1823371 ,2954,2954,2954
BEGIN DESCRIPTION:
Guadalupe River - 56
END DESCRIPTION:
XS GIS Cut Line= 3
      2096236.27     13871930.06       2092873.2     13873131.15
       2090831.4     13873341.34
#Sta/Elev= 30
  2609.4 1219.98  2846.4 1211.73  3591.7 1187.87  4155.5 1142.28  4203.5 1131.28
    4335 1125.53  4427.4 1140.01  4601.3  1141.5  4734.5 1133.78  4781.9 1117.19
  4842.5 1109.92  4861.9 1096.87  4891.3 1084.07  4937.3 1081.07  4977.8 1081.07
  5010.6 1097.92  5139.9 1125.66  5245.8 1131.91  5319.3 1138.91  5350.3 1162.67
  5445.9 1215.02  5562.7 1227.74  7132.3 1233.92  7243.1 1235.18  7507.8 1239.87
  7736.6 1241.92    7740 1241.88  8031.3 1250.68    8038 1250.64  8233.1 1254.07
#Mann= 13 ,-1 , 0
  2609.4     .07       0  2846.4     .12       0  4781.9     .05       0
  4861.9     .04       0  5010.6     .12       0  5245.8     .12       0
  7132.3     .07       0  7243.1     .12       0  7507.8     .07       0
  7736.6     .12       0    7740     .07       0  8031.3     .12       0
    8038     .07       0
Bank Sta=4861.9,5010.6
XS Rating Curve= 0 ,0
Exp/Cntr=0.3,0.1

Type RM Length L Ch R = 1 ,1820417 ,4182,4182,4182
BEGIN DESCRIPTION:
Guadalupe River - 55
END DESCRIPTION:
XS GIS Cut Line= 3
      2096746.69      13871509.7      2093173.47     13870008.35
      2093293.49     13867608.06
#Sta/Elev= 30
  2070.9 1243.62  2126.9 1242.95  2323.9  1233.6  3120.6 1201.88    3171 1200.42
  3450.7 1183.57  3526.2 1166.02    3598 1160.52  3703.5 1155.76  3919.2 1141.06
  4703.2 1127.45  4880.3 1092.33  4937.1 1077.87  5048.8 1080.87  5068.3 1096.98
  5168.7 1116.71  5192.5 1154.99  5286.4 1200.43  5502.2 1208.91  5562.3 1211.52
  5860.9 1222.02  5919.5 1221.45  6911.3 1217.08  7455.5 1228.41  7587.9  1230.2
  7842.4 1231.26  7902.5 1240.64  8007.4  1242.9  8137.3 1246.64    8350 1254.81
#Mann= 20 ,-1 , 0
  2070.9     .12       0  2126.9     .07       0  2323.9     .12       0
  3120.6     .07       0    3171     .05       0  3450.7     .07       0
    3598     .05       0  3703.5     .07       0  3919.2     .05       0
  4880.3     .04       0  5068.3     .05       0  5286.4     .07       0
  5502.2     .12       0  5562.3     .07       0  5860.9     .05       0
  5919.5     .07       0  7455.5     .05       0  7587.9     .07       0
  8007.4     .05       0  8137.3     .07       0
Bank Sta=4880.3,5068.3
XS Rating Curve= 0 ,0
Exp/Cntr=0.3,0.1

Type RM Length L Ch R = 1 ,1816235 ,3371,3371,3371
BEGIN DESCRIPTION:
Guadalupe River - 54
END DESCRIPTION:
XS GIS Cut Line= 4
      2097167.06     13871449.63      2097527.38     13869557.94
      2096896.82     13867516.11      2097407.27     13866104.87
#Sta/Elev= 30
  1726.6 1247.44  1825.9 1247.69  2114.7 1241.25  2565.6 1217.05  2906.7 1209.28
  3436.8 1199.53  3548.8  1193.1  3705.9 1185.28  4019.5 1159.49  4561.7 1130.34
  4665.6 1118.51  4733.4 1096.14  4953.2  1086.6  4971.2  1075.1    5020  1072.1
  5057.8 1076.84  5070.2 1087.06    5152 1111.65  5225.3 1119.79  5238.6 1149.95
  5289.3  1170.2  5303.9 1180.15  5393.3 1203.36  5712.2 1223.42  5910.8 1230.73
  6634.3 1257.02  6800.9 1259.32  7136.5 1263.46  7257.6 1261.97    7290 1261.21
#Mann= 20 ,-1 , 0
  1726.6     .05       0  1825.9     .07       0  2565.6     .05       0
  2906.7     .07       0  3436.8     .07       0  3548.8     .05       0
  3705.9     .05       0  4019.5     .07       0  4561.7     .12       0
  4665.6     .07       0  4953.2     .04       0  5070.2     .12       0
  5289.3     .12       0  5393.3     .08       0  5712.2     .05       0
  5910.8     .05       0  6634.3     .05       0  6800.9     .05       0
  7136.5     .12       0  7257.6     .05       0
Bank Sta=4953.2,5070.2
XS Rating Curve= 0 ,0
Exp/Cntr=0.3,0.1

Type RM Length L Ch R = 1 ,1812864 ,3429,3429,3429
BEGIN DESCRIPTION:
Guadalupe River - 53
END DESCRIPTION:
XS GIS Cut Line= 4
      2099749.38     13870368.69      2100199.79     13868657.13
      2099899.52     13866194.92      2097558.73      13865534.7
#Sta/Elev= 30
  2543.1 1226.23  2572.9 1225.79  2725.1  1221.3  2875.6 1218.09  2976.5 1215.52
  3964.4 1198.82  4236.4  1184.8  4728.7 1139.74  4818.8 1102.51  4891.9 1087.28
  4909.5 1075.75    4969 1069.66  5020.3    1076  5040.4 1089.95  5110.9 1106.57
  5419.9 1120.88    5747 1148.05  5982.5 1160.56  6278.4  1191.1  6788.8 1208.36
  7128.4 1204.89  7462.7 1200.59  7660.8 1204.43  7991.5 1212.43    8093 1216.45
  8184.8 1219.27  8777.6  1225.6  9023.8 1232.98  9209.6 1238.86  9225.5 1240.04
#Mann= 20 ,-1 , 0
  2543.1     .05       0  2572.9     .07       0  2725.1     .05       0
  2875.6     .07       0  2976.5     .12       0  4891.9     .04       0
  5040.4     .12       0  5419.9     .07       0    5747     .07       0
  5982.5     .05       0  6278.4     .12       0  7128.4     .05       0
  7462.7     .12       0  7660.8     .05       0  7991.5     .12       0
    8093     .07       0  8184.8     .05       0  8777.6     .07       0
  9023.8     .12       0  9209.6     .05       0
Bank Sta=4891.9,5040.4
XS Rating Curve= 0 ,0
Exp/Cntr=0.3,0.1

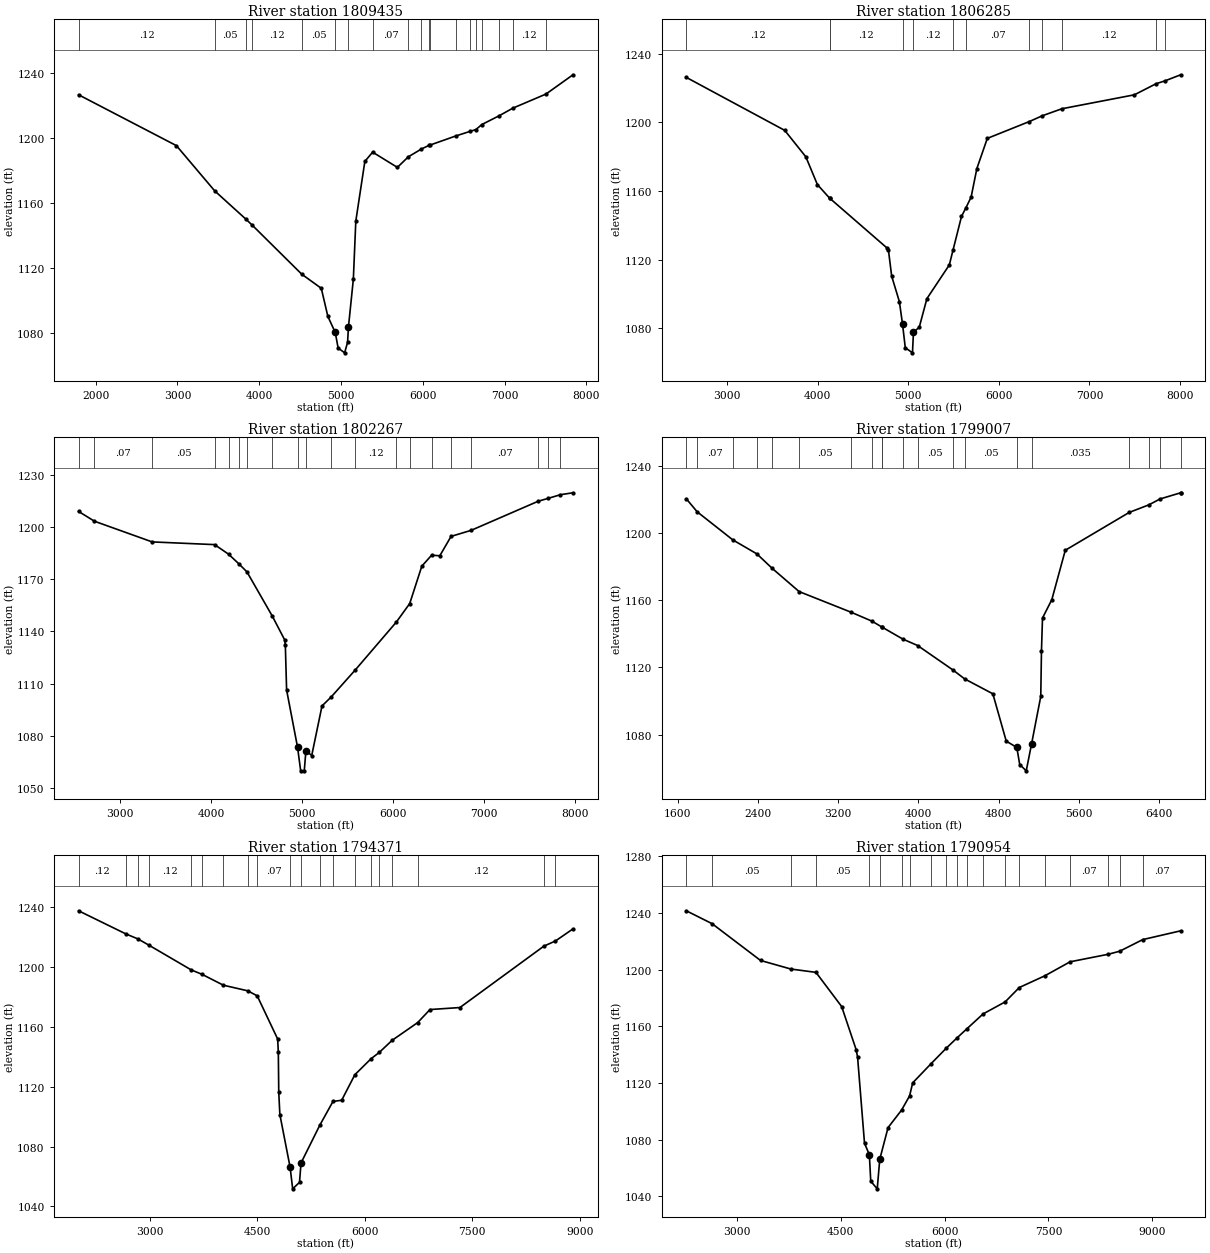
Type RM Length L Ch R = 1 ,1809435 ,3150,3150,3150
BEGIN DESCRIPTION:
Guadalupe River - 52
END DESCRIPTION:
XS GIS Cut Line= 4
      2101520.98     13869888.23      2102932.24     13868056.59
      2103082.37     13866495.19       2105034.1     13865564.37
#Sta/Elev= 30
  1792.1 1226.88  2987.9 1195.53  3456.1 1167.64  3837.5  1150.2  3909.1 1146.78
  4520.4 1116.27    4759 1107.58  4839.3 1090.26  4929.7 1080.35  4964.7 1070.81
  5044.1 1067.81  5080.4 1074.32  5090.5 1083.53  5150.8 1113.16  5180.9 1149.02
  5291.4  1185.8  5386.5 1191.51  5688.8 1182.12    5823 1188.64  5983.5 1193.47
  6077.2 1195.71  6091.5 1195.93  6399.8 1201.43  6573.9 1204.25  6648.4 1205.42
  6721.4 1208.53  6936.1 1214.02    7100 1218.62  7505.5 1227.32  7835.3  1239.2
#Mann= 19 ,-1 , 0
  1792.1     .12       0  3456.1     .05       0  3837.5     .07       0
  3909.1     .12       0  4520.4     .05       0  4929.7     .04       0
  5090.5     .05       0  5386.5     .07       0    5823     .05       0
  5983.5     .07       0  6077.2     .12       0  6091.5     .05       0
  6399.8     .07       0  6573.9     .12       0  6648.4     .07       0
  6721.4     .12       0  6936.1     .07       0    7100     .12       0
  7505.5     .07       0
Bank Sta=4929.7,5090.5
XS Rating Curve= 0 ,0
Exp/Cntr=0.3,0.1

Type RM Length L Ch R = 1 ,1806285 ,4018,4018,4018
BEGIN DESCRIPTION:
Guadalupe River - 51
END DESCRIPTION:
XS GIS Cut Line= 3
      2103232.54     13870819.05      2105544.59     13868476.97
      2105694.72     13866315.01
#Sta/Elev= 30
  2549.8 1226.14  3636.3 1195.28  3869.6 1179.86  3996.9  1163.7  4131.2 1155.83
  4131.9  1155.8  4767.7 1126.66  4781.8 1125.35  4817.2 1110.33  4902.1 1095.53
  4937.4 1082.23  4967.3 1068.68  5046.8 1065.68  5057.6  1077.7  5121.3 1080.54
  5206.1 1097.26  5453.6  1116.9  5494.8  1125.6    5588 1145.13  5636.9 1150.19
    5694 1156.34  5757.7 1173.05  5872.9  1190.6  6337.2 1200.42    6479 1203.76
  6695.7 1207.86  7496.8 1215.99    7736 1222.44  7834.4 1224.12    8008 1227.66
#Mann= 12 ,-1 , 0
  2549.8     .12       0  4131.2     .05       0  4131.9     .12       0
  4937.4     .04       0  5057.6     .12       0  5494.8     .12       0
  5636.9     .07       0  6337.2     .12       0    6479     .07       0
  6695.7     .12       0    7736     .05       0  7834.4     .07       0
Bank Sta=4937.4,5057.6
XS Rating Curve= 0 ,0
Exp/Cntr=0.3,0.1

Type RM Length L Ch R = 1 ,1802267 ,3260,3260,3260
BEGIN DESCRIPTION:
Guadalupe River - 50
END DESCRIPTION:
XS GIS Cut Line= 4
      2106145.12     13873821.79      2106805.72     13872260.37
      2108367.12     13870578.86      2108277.11     13869138.74
#Sta/Elev= 30
  2541.3 1208.99    2716 1203.35    3350 1191.46  4036.2  1189.9  4189.3 1184.41
  4300.9 1178.95  4391.5 1174.23  4670.4 1148.77  4805.9 1135.14  4813.3 1132.37
  4827.4 1106.29  4947.6  1073.4  4982.1 1059.78  5021.6 1059.78  5039.5 1071.36
  5103.5  1068.6  5216.4 1097.11    5318 1102.31  5584.1 1117.93  6033.2 1145.34
  6180.3 1156.01  6313.3 1177.51  6420.7  1183.8  6511.2  1183.5  6634.8 1194.65
  6854.2 1198.09  7592.4 1214.86  7696.6 1216.43  7836.3 1218.61  7974.3 1219.72
#Mann= 20 ,-1 , 0
  2541.3     .07       0    2716     .07       0    3350     .05       0
  4036.2     .07       0  4189.3     .05       0  4300.9     .07       0
  4391.5     .05       0  4670.4     .07       0  4947.6     .04       0
  5039.5     .12       0    5318     .05       0  5584.1     .12       0
  6033.2     .07       0  6180.3     .12       0  6420.7     .07       0
  6634.8     .12       0  6854.2     .07       0  7592.4     .05       0
  7696.6     .07       0  7836.3     .07       0
Bank Sta=4947.6,5039.5
XS Rating Curve= 0 ,0
Exp/Cntr=0.3,0.1

Type RM Length L Ch R = 1 ,1799007 ,4636,4636,4636
BEGIN DESCRIPTION:
Guadalupe River - 49
END DESCRIPTION:
XS GIS Cut Line= 2
      2106265.23     13874332.23      2111039.56     13873101.12
#Sta/Elev= 30
  1685.3 1220.39  1793.7 1212.64  2149.4  1195.9  2389.2 1187.57  2540.6 1179.02
  2810.2 1165.13  3332.5 1152.74  3537.7 1147.48  3639.7 1143.87  3640.2 1143.86
  3845.4 1136.81  3991.9 1133.01    4344 1118.45  4460.9 1113.13  4742.5 1104.24
  4876.1 1076.04  4981.4 1072.31  5010.4 1062.13  5075.4 1058.36  5129.2  1074.6
  5220.3 1102.69  5227.3 1129.79  5237.6 1149.37  5330.5  1160.3  5464.8 1189.73
  6102.3 1212.27  6298.4 1216.78    6410 1220.29  6615.2 1223.96  6615.8 1223.97
#Mann= 20 ,-1 , 0
  1685.3     .05       0  1793.7     .07       0  2149.4     .05       0
  2389.2     .07       0  2540.6     .12       0  2810.2     .05       0
  3332.5     .12       0  3537.7     .05       0  3639.7     .12       0
  3640.2     .05       0  3845.4     .12       0  3991.9     .05       0
    4344     .12       0  4460.9     .05       0  4981.4     .04       0
  5129.2    .035       0  6102.3     .07       0  6298.4     .05       0
    6410     .12       0  6615.2     .07       0
Bank Sta=4981.4,5129.2
XS Rating Curve= 0 ,0
Exp/Cntr=0.3,0.1

Type RM Length L Ch R = 1 ,1794371 ,3417,3417,3417
BEGIN DESCRIPTION:
Guadalupe River - 48
END DESCRIPTION:
XS GIS Cut Line= 4
      2108036.81     13879256.68      2109748.36     13877425.01
       2111009.5     13875383.18      2111249.72     13873401.36
#Sta/Elev= 30
  2001.8 1237.61  2663.5 1222.11  2829.2 1218.83  2978.4 1214.77  3575.4 1198.06
  3724.7 1195.15  4023.2 1187.86  4365.1 1184.08    4496 1180.74  4781.6 1151.88
  4790.8 1143.07  4796.9 1116.32  4812.3  1101.4  4955.3 1066.18  4991.1 1051.71
  5086.6 1056.04  5108.1 1069.03  5370.1 1094.25    5554 1110.14  5675.4 1110.93
  5859.4 1127.99  6086.4 1138.74  6199.9 1142.88  6380.5 1151.03  6736.7 1162.86
  6908.6 1171.58  7326.5 1172.92  8498.9 1213.97    8661 1217.44  8904.9 1225.49
#Mann= 20 ,-1 , 0
  2001.8     .12       0  2663.5     .05       0  2829.2     .05       0
  2978.4     .12       0  3575.4     .05       0  3724.7     .05       0
  4023.2     .07       0  4365.1     .05       0    4496     .07       0
  4955.3     .04       0  5108.1     .07       0  5370.1     .07       0
    5554     .05       0  5859.4     .07       0  6086.4     .12       0
  6199.9     .05       0  6380.5     .05       0  6736.7     .12       0
  8498.9     .07       0    8661     .12       0
Bank Sta=4955.3,5108.1
XS Rating Curve= 0 ,0
Exp/Cntr=0.3,0.1

Type RM Length L Ch R = 1 ,1790954 ,4380,4380,4380
BEGIN DESCRIPTION:
Guadalupe River - 47
END DESCRIPTION:
XS GIS Cut Line= 4
       2111700.1     13879767.13      2112961.25     13877995.52
      2113081.36     13875293.09      2111790.22     13873431.45
#Sta/Elev= 30
    2267 1241.48  2640.3 1232.35  3339.8 1206.42  3778.1 1200.37  4140.7 1198.02
  4512.2  1173.9  4722.4 1143.37  4742.5 1138.11  4842.6  1077.4  4912.6 1069.32
  4932.7 1050.62  5026.6 1045.24  5062.8 1066.05  5182.9 1088.46  5379.1 1100.88
    5494 1110.84  5538.9 1120.04  5799.9 1133.33  6022.9 1144.44  6182.4  1151.9
  6324.5 1158.29  6555.2 1168.65  6875.5 1177.18  7079.4 1187.32  7448.9 1195.59
    7814 1205.47    8364 1210.78  8529.8 1212.92  8864.2 1221.15  9412.3 1227.34
#Mann= 20 ,-1 , 0
    2267     .12       0  2640.3     .05       0  3778.1     .07       0
  4140.7     .05       0  4912.6     .04       0  5062.8     .12       0
  5379.1     .07       0    5494     .12       0  5799.9     .07       0
  6022.9     .05       0  6182.4     .07       0  6324.5     .07       0
  6555.2     .12       0  6875.5     .07       0  7079.4     .12       0
  7448.9     .05       0    7814     .07       0    8364     .12       0
  8529.8     .12       0  8864.2     .07       0
Bank Sta=4912.6,5062.8
XS Rating Curve= 0 ,0
Exp/Cntr=0.3,0.1