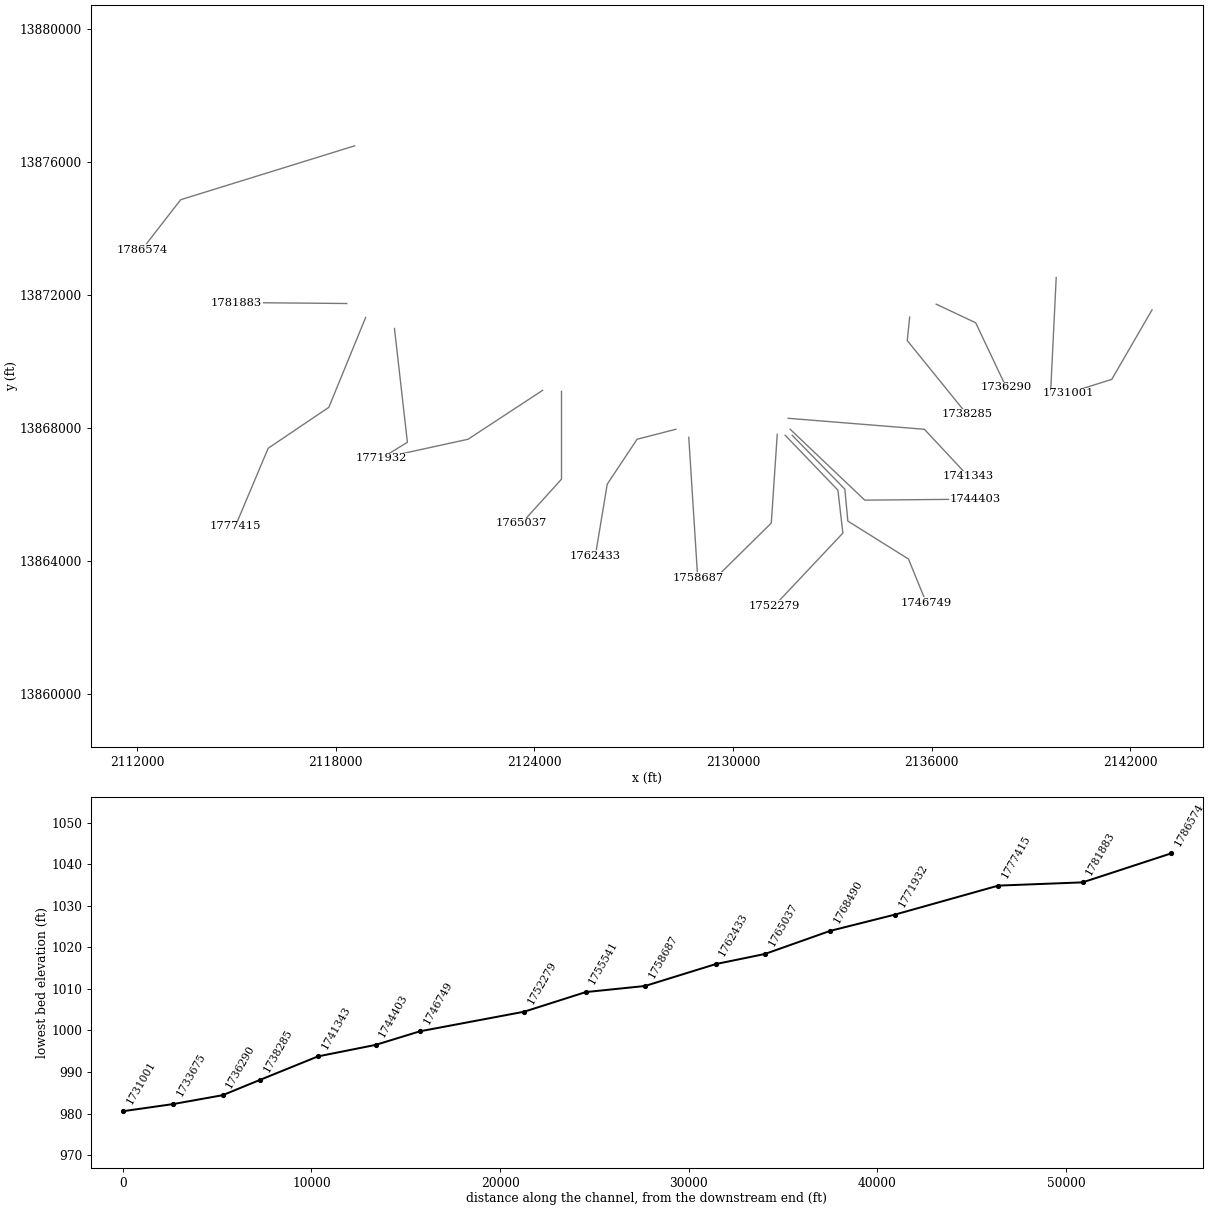
HEC-RAS study Guadalupe River.prj: Guadalupe River Base Level Engineering

--- Guadalupe River.g01 (geometry) --- (continued)

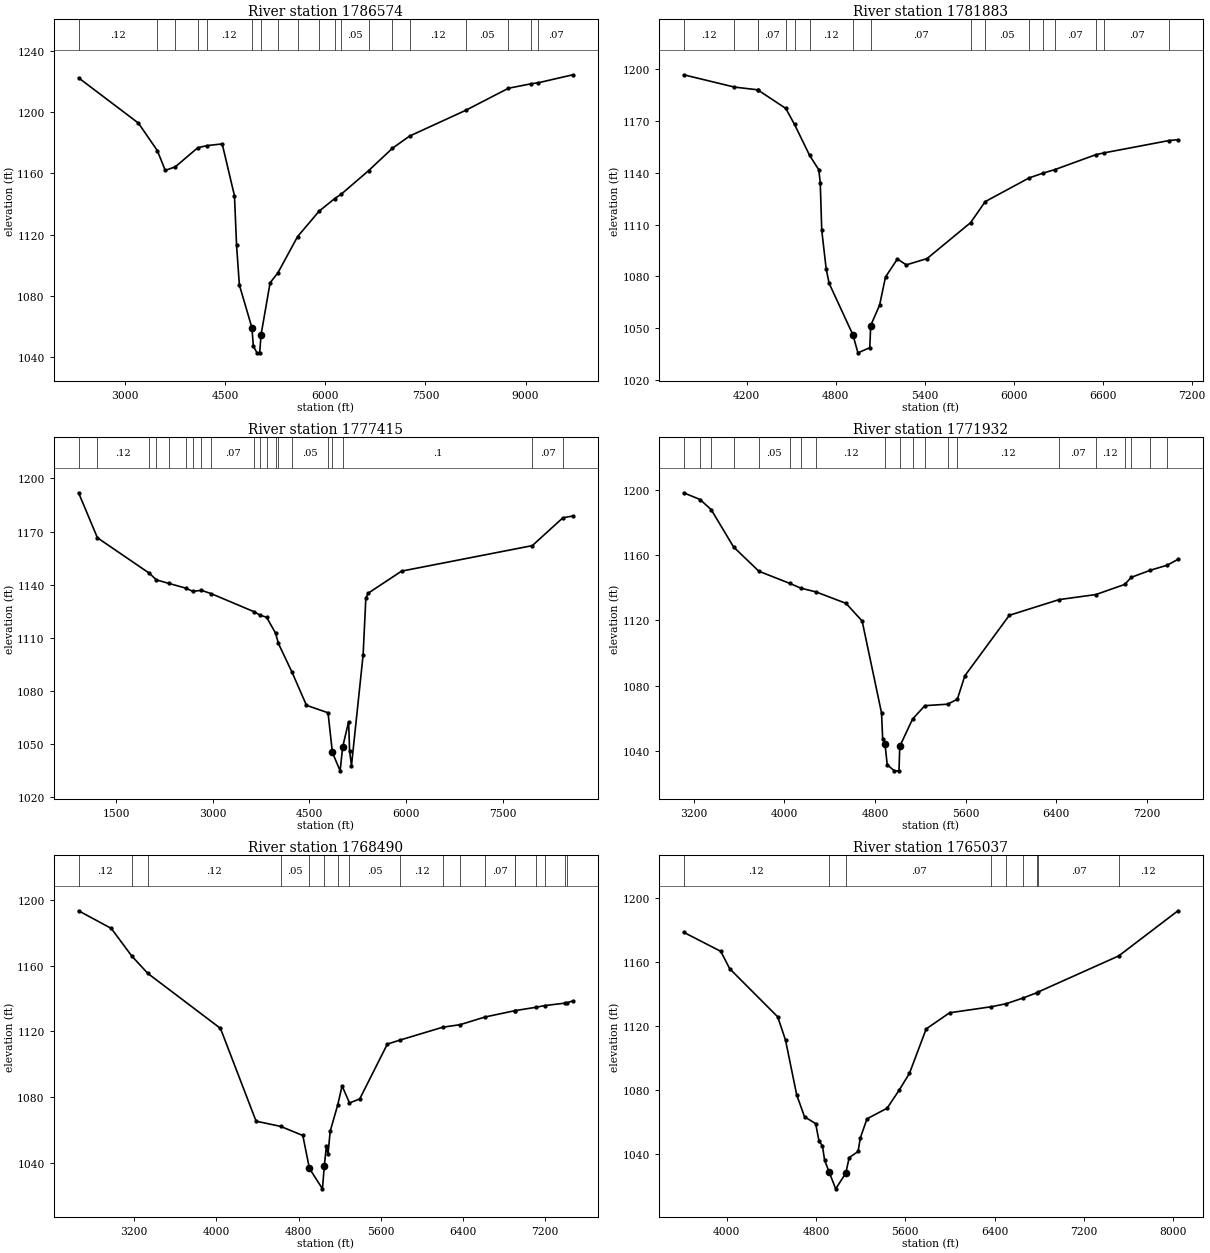
Type RM Length L Ch R = 1 ,1786574 ,4691,4691,4691
BEGIN DESCRIPTION:
Guadalupe River - 46
END DESCRIPTION:
XS GIS Cut Line= 3
      2118576.25     13876494.16      2113321.57     13874872.72
      2112150.53     13873371.38
#Sta/Elev= 30
  2304.5 1222.57  3200.5 1192.96  3483.6    1175  3602.8 1161.99  3753.2 1164.33
    4090 1176.83  4224.1 1178.19  4455.8 1179.34  4639.6 1145.34    4671 1112.89
  4712.8 1087.03  4901.3 1058.98  4922.1 1046.92  4977.6 1042.61  5017.3 1042.61
  5037.2 1054.33  5173.3 1088.47  5289.9 1094.97  5585.1 1118.71  5908.4 1135.37
  6139.9 1143.54  6242.1 1146.56  6650.8 1161.93  7005.8  1176.5  7263.7 1184.49
  8103.4 1201.31  8743.7 1215.77  9083.1 1218.68    9190 1219.35  9707.7 1224.57
#Mann= 19 ,-1 , 0
  2304.5     .12       0  3483.6     .07       0  3753.2     .12       0
    4090     .07       0  4224.1     .12       0  4901.3     .04       0
  5037.2     .12       0  5289.9     .05       0  5585.1     .12       0
  5908.4     .05       0  6139.9     .12       0  6242.1     .05       0
  6650.8     .12       0  7005.8     .07       0  7263.7     .12       0
  8103.4     .05       0  8743.7     .07       0  9083.1     .05       0
    9190     .07       0
Bank Sta=4901.3,5037.2
XS Rating Curve= 0 ,0
Exp/Cntr=0.3,0.1

Type RM Length L Ch R = 1 ,1781883 ,4468,4468,4468
BEGIN DESCRIPTION:
Guadalupe River - 45
END DESCRIPTION:
XS GIS Cut Line= 2
      2118336.09     13871749.91      2115003.13     13871779.94
#Sta/Elev= 30
  3774.2 1196.89  4116.1 1189.76  4272.2 1188.19  4273.6 1188.15  4462.8 1177.38
  4521.7  1168.1  4623.8  1150.1  4685.3 1141.81  4695.3 1134.23  4705.3 1106.72
  4735.3 1084.27  4755.3 1075.91  4915.3 1046.13  4949.3 1035.64  5029.4 1038.64
  5035.3 1051.46  5095.3 1063.27  5135.3 1079.61  5215.4 1090.07  5275.4 1086.65
  5415.4 1090.31    5709 1111.14  5807.5 1123.33  6103.3 1137.06  6198.7  1139.9
    6278 1141.92  6552.9 1150.54  6608.4  1151.6  7047.3 1158.75  7107.3 1159.27
#Mann= 17 ,-1 , 0
  3774.2     .12       0  4116.1     .07       0  4272.2     .05       0
  4273.6     .07       0  4462.8     .05       0  4521.7     .07       0
  4623.8     .12       0  4915.3     .04       0  5035.3     .07       0
    5709     .12       0  5807.5     .05       0  6103.3     .07       0
  6198.7     .12       0    6278     .07       0  6552.9     .12       0
  6608.4     .07       0  7047.3     .12       0
Bank Sta=4915.3,5035.3
XS Rating Curve= 0 ,0
Exp/Cntr=0.3,0.1

Type RM Length L Ch R = 1 ,1777415 ,5483,5483,5483
BEGIN DESCRIPTION:
Guadalupe River - 44
END DESCRIPTION:
XS GIS Cut Line= 4
      2118906.57     13871329.49      2117795.59     13868627.11
      2115963.95       13867396.      2114973.04     13865053.86
#Sta/Elev= 30
   917.2  1191.9    1210 1166.48    2017 1146.43  2124.7  1142.7  2313.5 1140.77
  2578.2 1138.07  2691.4 1136.23  2823.3  1136.8  2973.9 1134.96  3638.8 1124.76
  3727.9 1122.91  3835.7 1121.54  3975.1 1112.62    4018 1106.87  4230.8 1090.51
  4454.2 1071.87  4789.4 1067.65  4856.8 1045.22    4977 1034.86  5015.8 1048.24
  5108.8 1062.63  5123.8 1046.06  5153.1 1037.86  5333.7 1100.34  5375.8 1132.36
  5411.8 1135.18  5930.7 1147.65  7959.3 1162.05  8434.1 1177.75  8589.1 1178.81
#Mann= 20 ,-1 , 0
   917.2     .05       0    1210     .12       0    2017     .05       0
  2124.7     .05       0  2313.5     .07       0  2578.2     .12       0
  2691.4     .07       0  2823.3     .12       0  2973.9     .07       0
  3638.8     .12       0  3727.9     .07       0  3835.7     .05       0
  3975.1     .07       0    4018     .12       0  4230.8     .05       0
  4789.4     .12       0  4856.8     .04       0  5015.8      .1       0
  7959.3     .07       0  8434.1     .12       0
Bank Sta=4856.8,5015.8
XS Rating Curve= 0 ,0
Exp/Cntr=0.3,0.1

Type RM Length L Ch R = 1 ,1771932 ,3442,3442,3442
BEGIN DESCRIPTION:
Guadalupe River - 43
END DESCRIPTION:
XS GIS Cut Line= 3
      2119777.37     13870999.27      2120167.72     13867576.16
      2119388.54     13867096.66
#Sta/Elev= 30
  3112.6 1198.24  3257.1 1194.12  3355.8 1187.88  3553.1 1165.02  3775.9 1150.18
  4046.5 1142.78    4148 1139.77  4280.2  1137.5  4544.5  1130.5    4687 1119.68
  4858.1 1063.32  4868.2 1047.24  4888.3 1044.41  4908.4 1031.53  4971.9 1027.88
  5011.9 1027.88  5019.1 1042.89  5131.9 1059.64  5240.6 1067.82  5440.7 1068.71
  5526.6 1071.72  5592.8 1086.09  5985.4 1123.18  6424.9  1132.8  6748.3 1135.87
  7002.4 1142.08  7061.3 1146.44  7229.5 1150.79  7377.8 1153.87  7472.8 1157.45
#Mann= 20 ,-1 , 0
  3112.6     .07       0  3257.1     .12       0  3355.8     .05       0
  3553.1     .07       0  3775.9     .05       0  4046.5     .12       0
    4148     .07       0  4280.2     .12       0  4888.3     .04       0
  5019.1    .035       0  5131.9     .05       0  5240.6     .07       0
  5440.7     .05       0  5526.6     .12       0  6424.9     .07       0
  6748.3     .12       0  7002.4     .07       0  7061.3     .12       0
  7229.5     .07       0  7377.8     .12       0
Bank Sta=4888.3,5019.1
XS Rating Curve= 0 ,0
Exp/Cntr=0.3,0.1

Type RM Length L Ch R = 1 ,1768490 ,3453,3453,3453
BEGIN DESCRIPTION:
Guadalupe River - 42
END DESCRIPTION:
XS GIS Cut Line= 3
      2124251.43     13869137.59      2121999.37     13867666.24
      2119928.73      13867216.1
#Sta/Elev= 30
  2659.8 1193.43    2978 1182.68  3175.4 1166.01  3333.8 1155.24  4040.1 1121.76
  4386.9 1065.19    4625 1062.03  4841.5 1056.47  4905.7 1036.41  5032.6 1023.95
  5050.5 1037.82  5071.6  1050.3  5086.7    1045  5107.8 1059.07  5180.2 1074.85
  5223.7 1086.71  5295.6  1076.3  5395.3 1078.75  5664.1 1112.19  5789.1 1114.66
  6204.4 1122.49    6371 1123.99  6614.2 1128.68  6905.6 1132.56    6910  1132.6
    7106 1134.57  7198.5 1135.67  7397.1 1137.17  7414.3 1137.38  7468.9 1138.51
#Mann= 18 ,-1 , 0
  2659.8     .12       0  3175.4     .07       0  3333.8     .12       0
    4625     .05       0  4905.7     .04       0  5050.5    .035       0
  5180.2     .07       0  5295.6     .05       0  5789.1     .12       0
  6204.4     .07       0    6371     .12       0  6614.2     .07       0
  6905.6     .12       0    6910     .07       0    7106     .12       0
  7198.5     .07       0  7397.1     .12       0  7414.3     .07       0
Bank Sta=4905.7,5050.5
XS Rating Curve= 0 ,0
Exp/Cntr=0.3,0.1

Type RM Length L Ch R = 1 ,1765037 ,2604,2604,2604
BEGIN DESCRIPTION:
Guadalupe River - 41
END DESCRIPTION:
XS GIS Cut Line= 3
       2124821.9     13869107.54       2124821.9     13866465.16
      2123620.83     13865143.99
#Sta/Elev= 30
  3614.6 1178.61  3947.1 1166.71  4027.1 1155.85  4457.1 1125.81  4527.1 1111.25
  4627.1 1077.09  4697.1 1063.42  4797.1 1059.12  4827.1 1048.13  4857.1  1045.4
  4877.1 1036.35  4917.1 1028.98  4976.6  1018.4  5067.1  1028.2  5097.1 1037.88
  5177.1 1041.74  5197.1  1050.2  5257.1 1062.14  5437.1 1068.74  5547.1 1080.26
  5637.1 1090.51  5787.1 1118.26  5997.1 1128.35  6370.2 1132.11  6504.4 1134.01
  6653.6 1137.53  6777.9 1140.87  6790.3 1141.33  7511.9 1163.86  8042.5 1192.04
#Mann= 9 ,-1 , 0
  3614.6     .12       0  4917.1     .04       0  5067.1     .07       0
  6370.2     .07       0  6504.4     .12       0  6653.6     .07       0
  6777.9     .12       0  6790.3     .07       0  7511.9     .12       0
Bank Sta=4917.1,5067.1
XS Rating Curve= 0 ,0
Exp/Cntr=0.3,0.1

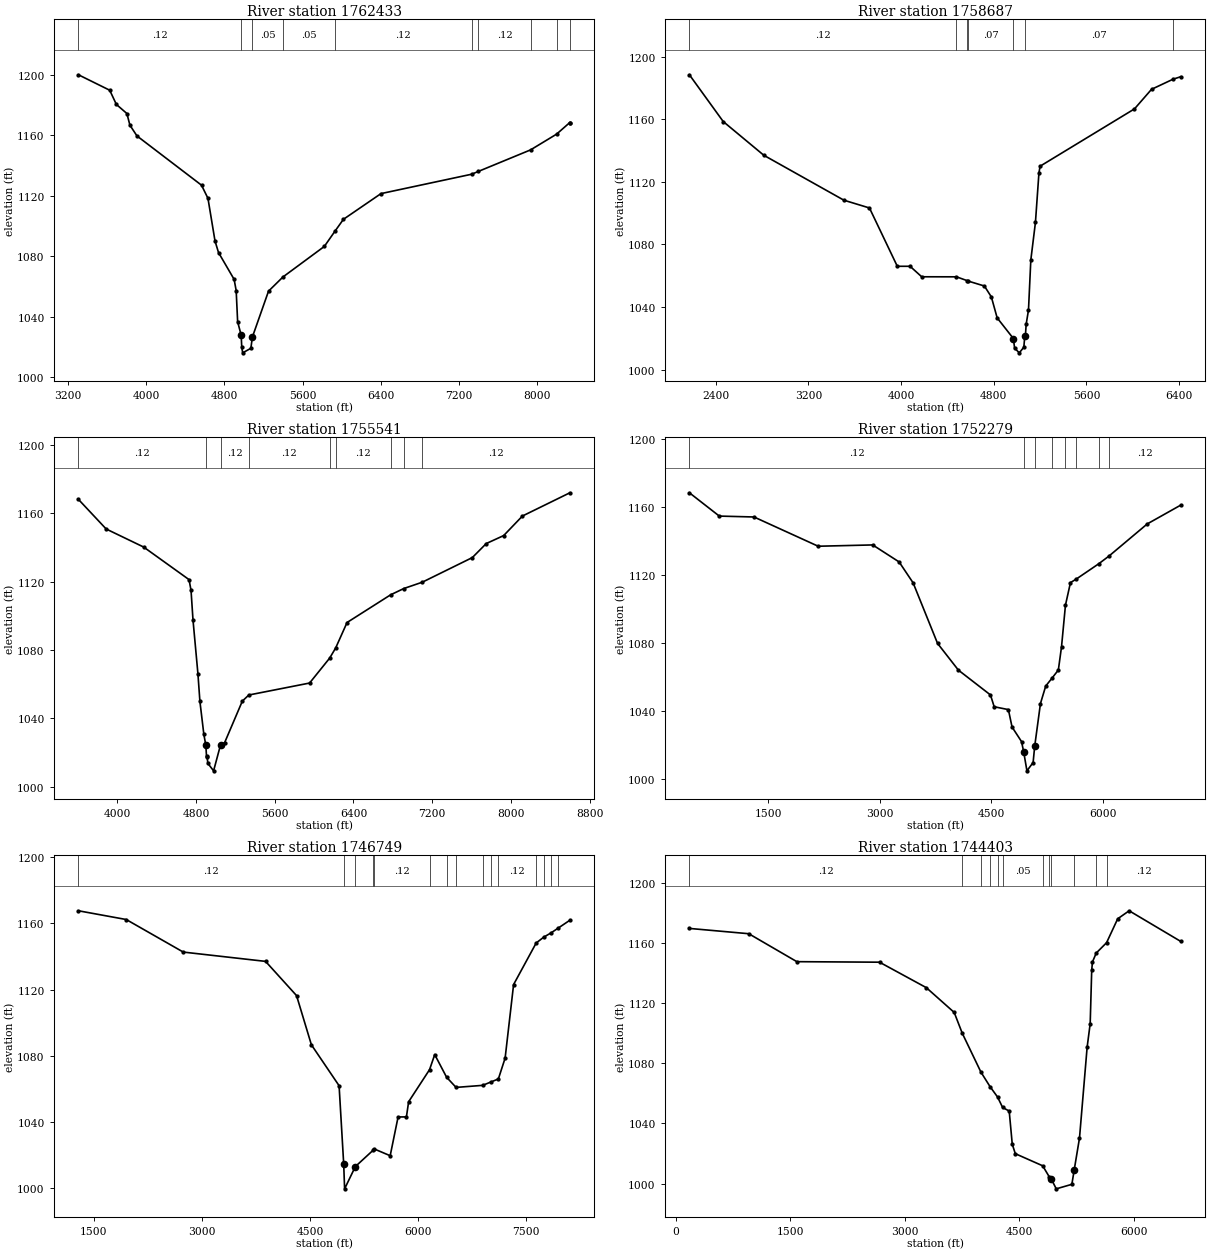
Type RM Length L Ch R = 1 ,1762433 ,3746,3746,3746
BEGIN DESCRIPTION:
Guadalupe River - 40
END DESCRIPTION:
XS GIS Cut Line= 4
      2128274.97      13867966.5      2127103.95     13867666.24
      2126203.14     13866315.03      2125842.82      13864153.1
#Sta/Elev= 30
  3307.6 1199.96  3627.6 1189.73  3695.4 1180.35  3803.1 1174.32  3834.1 1166.59
  3906.3 1159.48  4566.1  1126.9    4632 1118.19  4704.1 1089.96  4740.1  1082.3
  4899.4 1064.59  4920.4  1057.2  4935.4 1036.54  4971.5 1027.66  4977.5 1019.64
    4987 1015.97  5070.8 1018.97  5085.7 1026.33  5251.1 1056.78  5398.7 1066.17
  5821.8 1086.38  5931.4 1096.55  6017.1 1104.33  6400.9 1121.33  7328.8 1134.17
  7396.3 1136.01  7930.3 1150.26  8196.3 1160.68  8331.3 1168.35  8332.2 1168.35
#Mann= 10 ,-1 , 0
  3307.6     .12       0  4971.5     .04       0  5085.7     .05       0
  5398.7     .05       0  5931.4     .12       0  7328.8     .07       0
  7396.3     .12       0  7930.3     .07       0  8196.3     .12       0
  8331.3     .07       0
Bank Sta=4971.5,5085.7
XS Rating Curve= 0 ,0
Exp/Cntr=0.3,0.1

Type RM Length L Ch R = 1 ,1758687 ,3146,3146,3146
BEGIN DESCRIPTION:
Guadalupe River - 39
END DESCRIPTION:
XS GIS Cut Line= 2
      2128665.36     13867726.27       2128935.6     13863492.48
#Sta/Elev= 30
  2172.3  1188.4  2464.2 1158.52  2814.9 1136.95  3506.3 1108.24  3726.7 1103.28
  3967.1 1066.01  4077.4 1066.01  4177.6 1059.31    4478 1059.28  4569.4 1056.85
  4576.6 1056.61  4718.7 1053.41  4778.9 1046.45    4829 1033.05  4969.2 1019.83
  4979.5  1013.7  5020.1  1010.7  5059.4 1014.29  5067.7 1021.71  5072.7 1021.47
  5079.5    1029  5099.5 1038.03  5119.6 1070.02  5159.6 1094.13  5189.7 1125.68
  5199.7 1129.97  6014.6 1166.61  6161.7 1179.11  6347.4 1185.57  6414.7 1187.18
#Mann= 7 ,-1 , 0
  2172.3     .12       0    4478     .07       0  4569.4     .05       0
  4576.6     .07       0  4969.2     .04       0  5067.7     .07       0
  6347.4     .07       0
Bank Sta=4969.2,5067.7
XS Rating Curve= 0 ,0
Exp/Cntr=0.3,0.1

Type RM Length L Ch R = 1 ,1755541 ,3262,3262,3262
BEGIN DESCRIPTION:
Guadalupe River - 38
END DESCRIPTION:
XS GIS Cut Line= 3
      2131337.76     13867816.38       2131157.6     13865143.98
       2129506.1     13863522.51
#Sta/Elev= 30
  3605.7 1168.09  3887.7 1150.76  4268.6 1140.19  4729.6 1121.13  4749.7 1114.86
  4769.7 1097.54  4819.8 1066.01  4839.9 1049.88    4880 1030.54    4900  1024.2
  4907.7 1017.15  4912.7 1017.96  4920.1 1013.64  4978.9 1009.23  5050.4 1024.61
  5090.4 1025.64  5270.9 1050.03  5336.9 1053.61  5954.2 1060.61  6158.4 1075.22
  6219.2 1081.14  6334.8 1096.04  6777.9 1112.26    6912 1115.94  7098.8 1119.62
  7607.6 1134.04    7749 1142.24  7925.9 1146.91  8116.8 1158.36  8598.6 1171.96
#Mann= 9 ,-1 , 0
  3605.7     .12       0    4900     .04       0  5050.4     .12       0
  5336.9     .12       0  6158.4     .07       0  6219.2     .12       0
  6777.9     .05       0    6912     .07       0  7098.8     .12       0
Bank Sta=4900,5050.4
XS Rating Curve= 0 ,0
Exp/Cntr=0.3,0.1

Type RM Length L Ch R = 1 ,1752279 ,5530,5530,5530
BEGIN DESCRIPTION:
Guadalupe River - 37
END DESCRIPTION:
XS GIS Cut Line= 4
      2131577.97     13867786.36       2133169.4     13866134.87
      2133319.54     13864843.71      2131248.86     13862652.99
#Sta/Elev= 30
   442.1  1168.2   844.2 1154.48  1310.8 1153.95  2173.7 1136.73  2906.6  1137.5
  3262.1 1127.48  3450.2 1115.17  3778.6 1079.54  4059.1 1063.79  4490.4 1049.18
  4540.1 1042.23  4731.1 1040.56  4780.4  1030.3  4907.8 1021.73  4936.2 1015.86
  4980.5 1004.51  5063.6 1009.41  5084.6 1018.89  5162.3 1044.15  5233.1 1054.42
  5322.2 1059.33    5403 1063.87  5445.5 1077.52  5498.5 1102.05  5565.6  1115.3
  5646.6 1117.49  5943.9 1126.34  6083.3 1130.93  6598.4 1149.87  7049.9 1160.97
#Mann= 8 ,-1 , 0
   442.1     .12       0  4936.2     .04       0  5084.6     .07       0
  5322.2     .12       0  5498.5     .05       0  5646.6     .12       0
  5943.9     .05       0  6083.3     .12       0
Bank Sta=4936.2,5084.6
XS Rating Curve= 0 ,0
Exp/Cntr=0.3,0.1

Type RM Length L Ch R = 1 ,1746749 ,2346,2346,2346
BEGIN DESCRIPTION:
Guadalupe River - 36
END DESCRIPTION:
XS GIS Cut Line= 5
      2131788.14     13867786.37      2133379.59     13866164.89
      2133469.67     13865204.03      2135301.32     13864063.01
       2135841.8     13862741.82
#Sta/Elev= 30
  1285.7  1167.5  1949.1 1162.23  2741.2 1142.59  3883.7 1136.98  4313.9 1116.34
  4519.8 1086.67  4904.4 1061.99  4968.1 1014.96  4980.9  999.79  5129.8 1013.21
  5381.4 1023.26  5387.9 1023.92  5613.6 1019.77  5723.4 1043.14    5839 1043.18
  5869.7 1052.32  6160.2 1071.68    6232 1080.76  6396.9 1067.09  6528.3 1060.97
  6896.8  1062.2  7010.5 1064.21  7115.5 1066.06  7209.4 1078.67  7326.9 1123.01
  7640.4 1148.07  7745.4 1151.59  7850.4 1154.26  7946.1 1157.06  8108.2  1161.8
#Mann= 15 ,-1 , 0
  1285.7     .12       0  4968.1     .04       0  5129.8    .035       0
  5381.4     .07       0  5387.9     .12       0  6160.2     .05       0
  6396.9     .07       0  6528.3     .12       0  6896.8     .07       0
  7010.5     .05       0  7115.5     .12       0  7640.4     .07       0
  7745.4     .05       0  7850.4     .07       0  7946.1     .12       0
Bank Sta=4968.1,5129.8
XS Rating Curve= 0 ,0
Exp/Cntr=0.3,0.1

Type RM Length L Ch R = 1 ,1744403 ,3060,3060,3060
BEGIN DESCRIPTION:
Guadalupe River - 35
END DESCRIPTION:
XS GIS Cut Line= 3
       2131728.1     13867966.52      2133980.13      13865834.6
      2137311.51     13865864.61
#Sta/Elev= 30
   179.5 1169.63   956.6 1166.11    1586 1147.53  2668.2 1147.18  3280.5 1130.26
  3645.5 1113.79  3750.7 1099.99  3995.5 1074.11    4114 1064.52  4212.5  1057.6
  4279.2 1050.63  4365.5 1048.21  4405.5 1026.17  4445.5 1019.89  4803.6 1011.84
  4887.7 1004.68  4915.5 1003.15  4981.2  996.52  5185.6  999.52  5215.5 1008.83
  5285.5 1030.26  5385.5 1090.67  5425.5 1106.32  5445.5 1141.99  5455.5 1147.38
  5504.7 1153.27  5640.1 1160.15  5785.6 1176.04  5935.6 1181.36  6612.1 1160.96
#Mann= 12 ,-1 , 0
   179.5     .12       0  3750.7     .07       0  3995.5     .05       0
    4114     .07       0  4212.5     .12       0  4279.2     .05       0
  4803.6     .07       0  4887.7     .12       0  4915.5     .04       0
  5215.5    .035       0  5504.7     .07       0  5640.1     .12       0
Bank Sta=4915.5,5215.5
XS Rating Curve= 0 ,0
Exp/Cntr=0.3,0.1

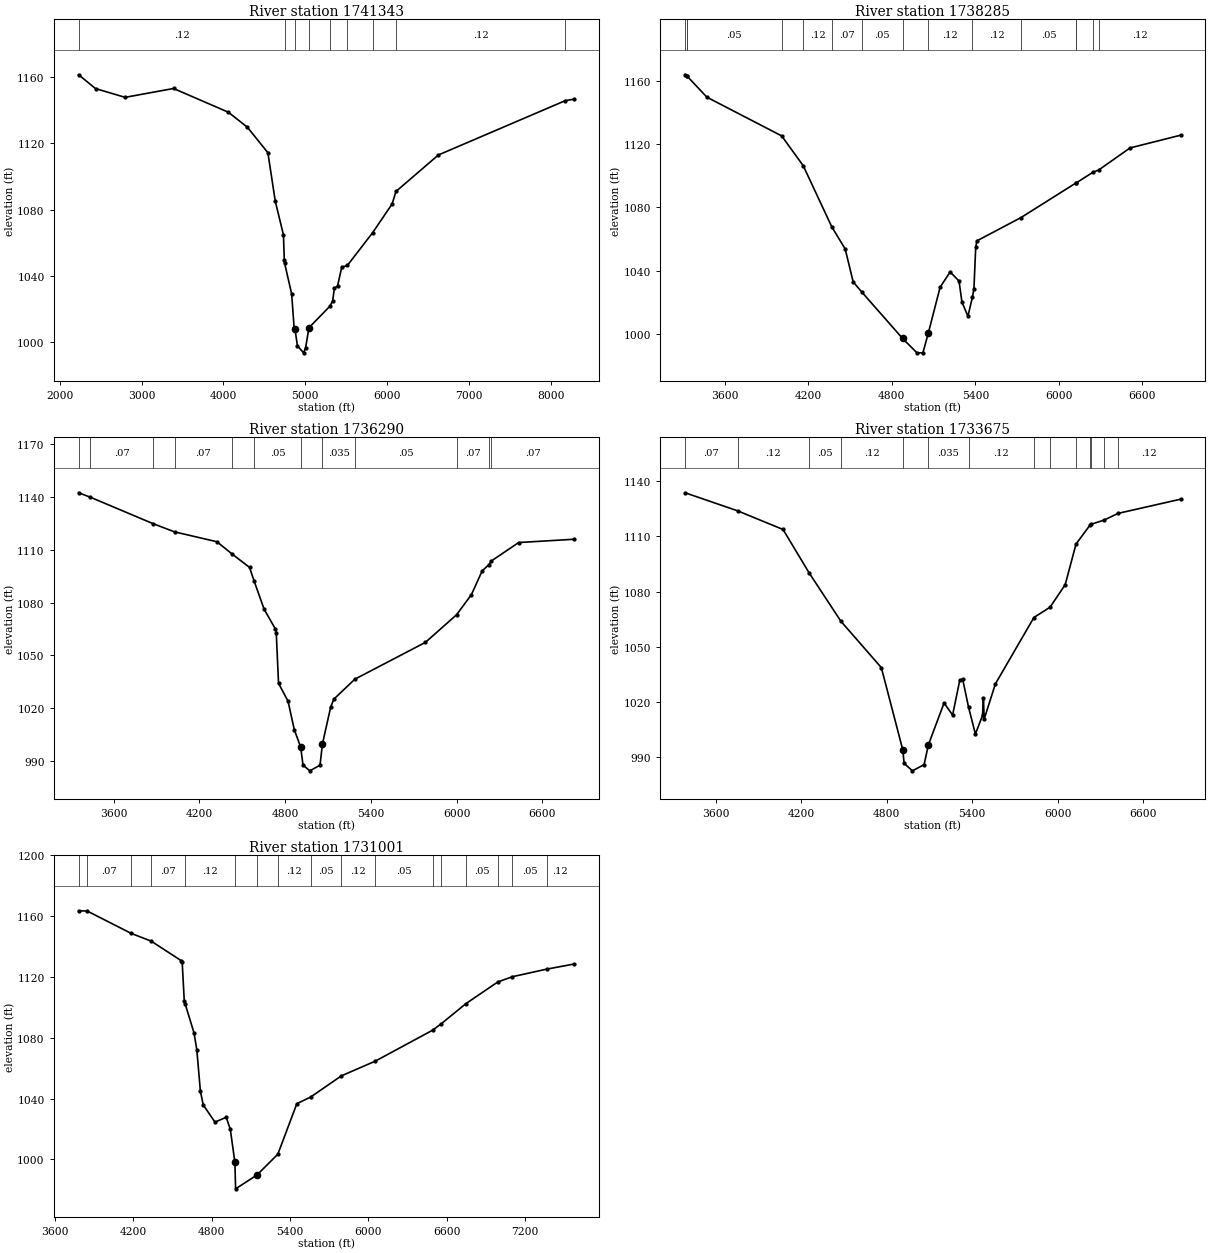
Type RM Length L Ch R = 1 ,1741343 ,3058,3058,3058
BEGIN DESCRIPTION:
Guadalupe River - 34
END DESCRIPTION:
XS GIS Cut Line= 3
      2131668.07     13868296.81      2135781.75     13867966.51
      2137102.93     13866555.25
#Sta/Elev= 30
  2229.2 1161.44  2435.5 1153.12    2798 1147.83  3389.9 1153.17  4060.3 1138.86
  4292.8 1129.82  4543.6 1114.44  4633.8 1085.24  4734.2 1064.83  4744.2 1049.79
  4748.7 1047.71  4834.5 1029.26  4864.6 1008.61  4874.6 1008.24  4904.7  997.99
  4980.2  993.75    5005  996.75  5045.2 1008.86  5303.4 1021.94  5336.1 1025.16
  5356.2 1032.56  5396.3 1034.21  5446.5 1045.37  5515.3 1046.43  5825.1 1066.24
    6063 1083.54  6109.9 1091.07  6628.4 1113.07  8180.8 1145.84  8289.3 1146.76
#Mann= 9 ,-1 , 0
  2229.2     .12       0  4748.7      .1       0  4874.6     .04       0
  5045.2     .07       0  5303.4     .12       0  5515.3     .07       0
  5825.1     .05       0  6109.9     .12       0  8180.8     .07       0
Bank Sta=4874.6,5045.2
XS Rating Curve= 0 ,0
Exp/Cntr=0.3,0.1

Type RM Length L Ch R = 1 ,1738285 ,1995,1995,1995
BEGIN DESCRIPTION:
Guadalupe River - 33
END DESCRIPTION:
XS GIS Cut Line= 3
      2135336.62     13871340.64      2135263.66      13870635.4
      2137063.22     13868422.43
#Sta/Elev= 30
  3314.3 1163.77  3324.6 1163.27  3325.2 1163.24  3470.8 1149.62  4008.2 1125.17
  4163.5 1106.29  4368.4 1067.73  4464.9 1053.72  4522.4 1032.89    4584 1026.55
  4877.2  997.21  4980.6  988.12  5023.3  988.12  5062.5 1000.67  5147.2 1029.63
  5219.1  1039.2    5283 1033.48  5303.8 1020.27  5346.9 1011.21  5379.1 1023.26
    5390  1028.6  5402.9 1054.78  5410.8 1058.84    5728 1073.55  6122.3 1095.37
  6124.1 1095.39  6245.3  1102.2  6286.4 1103.61  6511.9 1117.55  6875.6 1125.61
#Mann= 15 ,-1 , 0
  3314.3     .05       0  3324.6     .07       0  3325.2     .05       0
  4008.2     .07       0  4163.5     .12       0  4368.4     .07       0
    4584     .05       0  4877.2     .04       0  5062.5     .12       0
  5379.1     .12       0    5728     .05       0  6122.3     .07       0
  6124.1     .12       0  6245.3     .07       0  6286.4     .12       0
Bank Sta=4877.2,5062.5
XS Rating Curve= 0 ,0
Exp/Cntr=0.3,0.1

Type RM Length L Ch R = 1 ,1736290 ,2615,2615,2615
BEGIN DESCRIPTION:
Guadalupe River - 32
END DESCRIPTION:
XS GIS Cut Line= 3
      2136139.15     13871729.71      2137330.72      13871170.4
      2138254.82     13869224.93
#Sta/Elev= 30
  3353.9 1142.47  3433.5 1140.03  3875.3 1124.91  4025.4 1120.26  4322.5 1114.63
  4427.5 1107.73  4550.7 1100.05  4582.7 1092.32    4653 1076.26  4731.5 1065.07
  4737.8 1062.93  4753.7 1034.16  4820.1 1024.04  4864.4 1007.69  4908.7  997.96
  4925.1  987.68  4972.8  984.41  5044.2  987.62  5061.4  999.78    5119 1020.67
  5141.2 1025.17  5288.1 1036.51  5782.5 1057.45  6000.3 1073.12  6104.3 1084.56
  6179.9 1098.08  6226.3 1101.57  6244.3 1103.72  6435.4 1114.18    6824 1116.06
#Mann= 12 ,-1 , 0
  3353.9     .05       0  3433.5     .07       0  3875.3     .12       0
  4025.4     .07       0  4427.5     .12       0  4582.7     .05       0
  4908.7     .04       0  5061.4    .035       0  5288.1     .05       0
  6000.3     .07       0  6226.3     .12       0  6244.3     .07       0
Bank Sta=4908.7,5061.4
XS Rating Curve= 0 ,0
Exp/Cntr=0.3,0.1

Type RM Length L Ch R = 1 ,1733675 ,2674,2674,2674
BEGIN DESCRIPTION:
Guadalupe River - 31
END DESCRIPTION:
XS GIS Cut Line= 2
      2139762.56     13872532.26      2139592.33     13869054.73
#Sta/Elev= 30
  3382.6 1133.81  3751.3 1123.98  4070.7 1113.81  4255.1 1090.03  4477.7 1063.75
  4761.5 1038.52  4911.7   993.8  4921.7  986.32  4979.8  982.28  5061.9  985.67
  5091.9  996.45    5202 1019.25  5262.1 1012.69  5312.2 1031.57  5332.2 1032.39
  5374.3 1016.93  5422.3 1002.32  5472.4 1012.49  5478.8 1021.93  5483.8 1010.43
  5562.5 1029.63  5833.4 1065.84    5947 1071.47  6053.1 1083.71  6129.3 1105.87
    6228 1116.24  6233.2 1116.59  6326.6 1118.94  6425.3 1122.59  6864.3 1130.32
#Mann= 14 ,-1 , 0
  3382.6     .07       0  3751.3     .12       0  4255.1     .05       0
  4477.7     .12       0  4911.7     .04       0  5091.9    .035       0
  5374.3     .12       0  5833.4     .07       0    5947     .05       0
  6129.3     .12       0    6228     .07       0  6233.2     .12       0
  6326.6     .07       0  6425.3     .12       0
Bank Sta=4911.7,5091.9
XS Rating Curve= 0 ,0
Exp/Cntr=0.3,0.1

Type RM Length L Ch R = 1 ,1731001 ,3380,3380,3380
BEGIN DESCRIPTION:
Guadalupe River - 30
END DESCRIPTION:
XS GIS Cut Line= 3
      2142656.43     13871559.49      2141440.52     13869468.12
      2140128.64     13869055.12
#Sta/Elev= 30
  3781.8 1163.56  3847.3 1163.39  4183.4 1148.72  4336.6 1143.61  4569.2 1130.64
  4574.9 1129.52  4590.7 1104.11  4596.7 1102.51  4665.2 1083.23  4686.7 1072.11
    4714 1044.97  4735.5 1035.85  4825.7 1024.45  4911.8 1027.66  4943.2 1019.75
  4978.4  997.97  4983.7  980.55  5146.8  989.61    5307 1003.33  5452.7  1036.6
  5558.4 1040.97  5793.2 1054.89  6052.4 1064.56  6492.8 1084.98  6556.6 1089.07
  6746.7  1102.4  6991.4 1116.71  7103.9 1120.18  7364.9 1125.13  7576.3 1128.52
#Mann= 17 ,-1 , 0
  3781.8     .05       0  3847.3     .07       0  4183.4     .12       0
  4336.6     .07       0  4596.7     .12       0  4978.4     .04       0
  5146.8      .1       0    5307     .12       0  5558.4     .05       0
  5793.2     .12       0  6052.4     .05       0  6492.8     .12       0
  6556.6     .07       0  6746.7     .05       0  6991.4     .12       0
  7103.9     .05       0  7364.9     .12       0
Bank Sta=4978.4,5146.8
XS Rating Curve= 0 ,0
Exp/Cntr=0.3,0.1