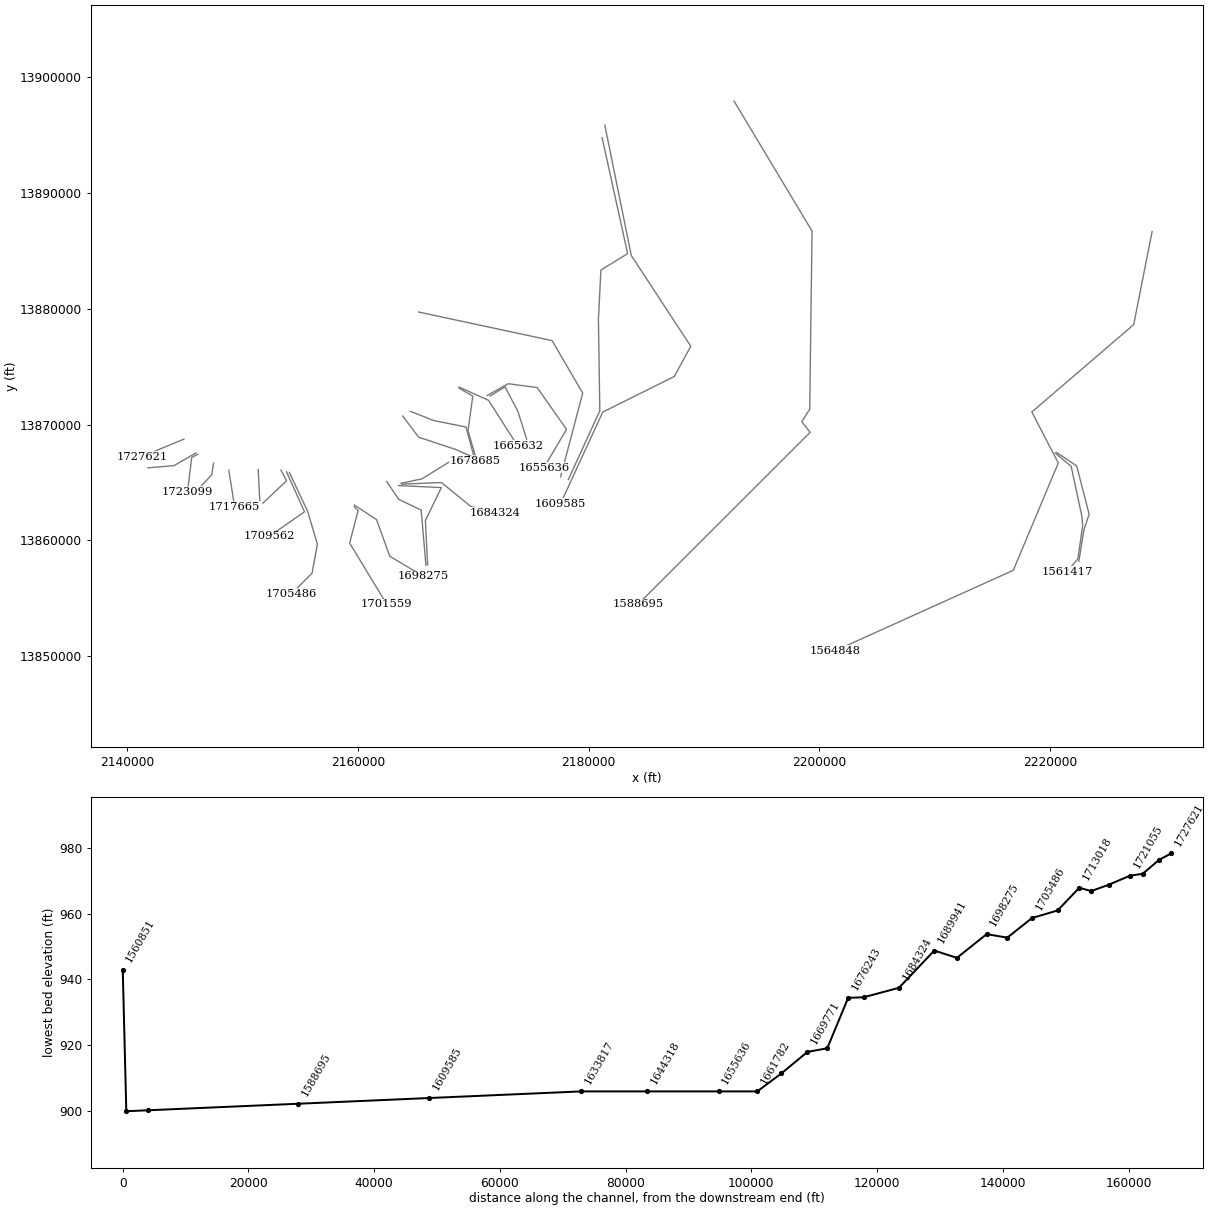
HEC-RAS study Guadalupe River.prj: Guadalupe River Base Level Engineering

--- Guadalupe River.g01 (geometry) --- (continued)

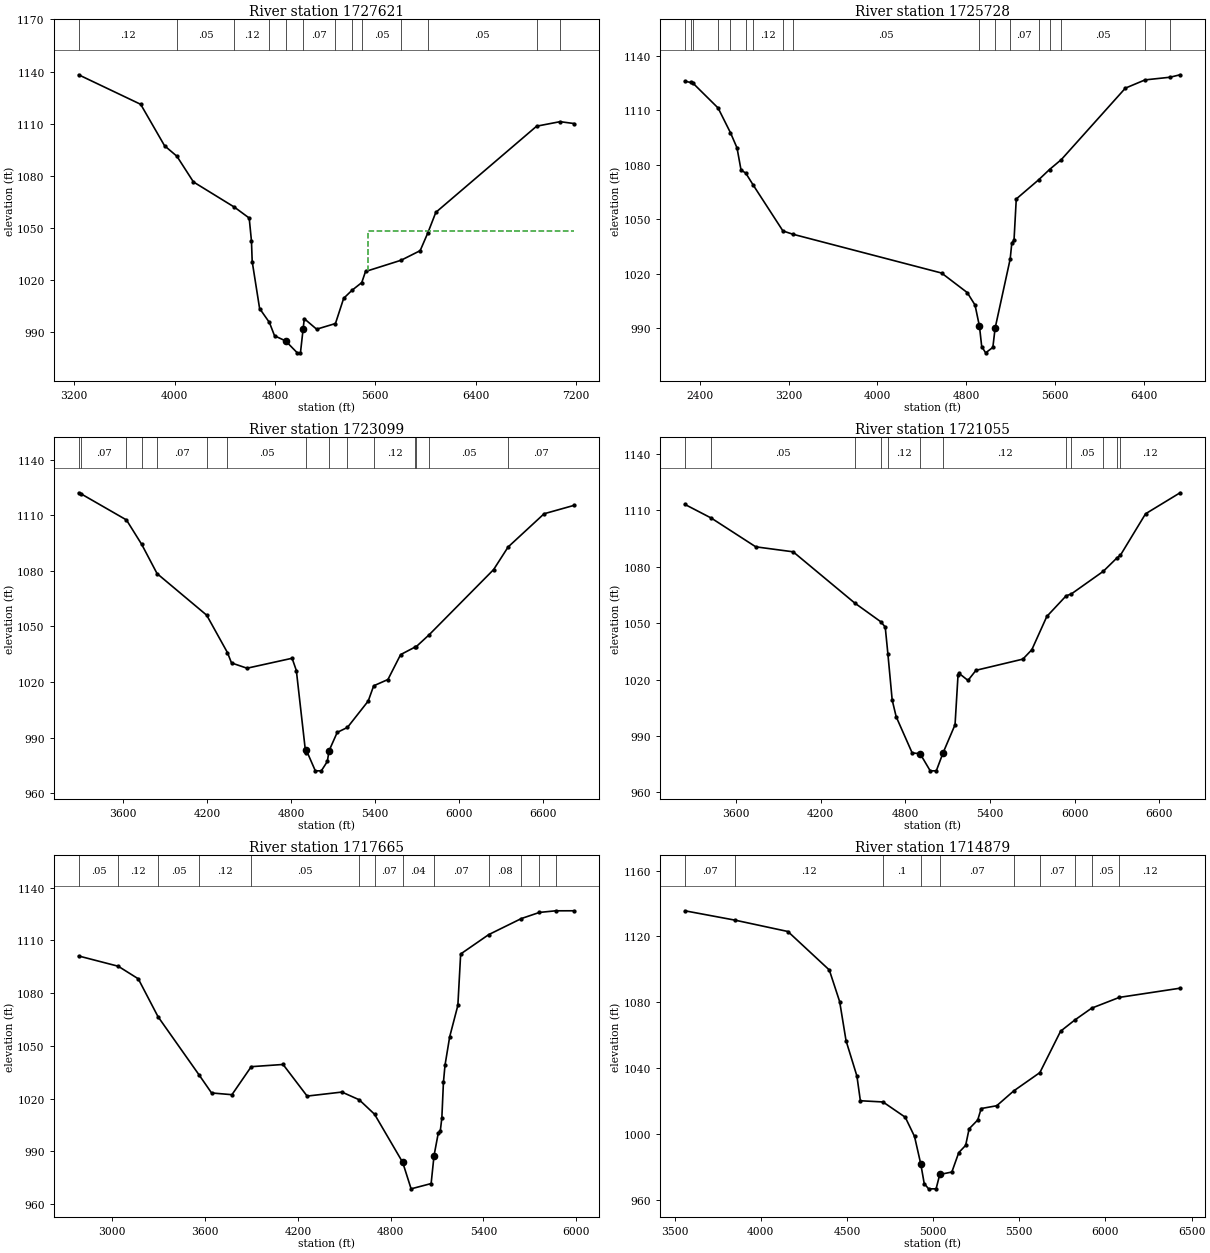
Type RM Length L Ch R = 1 ,1727621 ,1893,1893,1893
BEGIN DESCRIPTION:
Guadalupe River - 29
END DESCRIPTION:
XS GIS Cut Line= 2
      2144918.06     13868738.58      2141270.28     13867230.83
#Sta/Elev= 30
  3235.1 1138.13  3729.8 1121.14  3920.1 1097.31  4018.3  1091.3  4150.2 1076.51
  4476.2 1062.04  4594.5 1055.76  4612.6 1042.52  4618.4 1030.73  4677.5 1003.73
  4755.4  995.73  4796.6  988.04  4884.6  985.11  4977.7  978.25    5003  978.25
  5023.8  991.69  5033.5  997.88    5132  991.84  5281.9   995.1  5347.4  1009.6
  5412.5 1014.14  5491.5 1018.64  5521.5 1025.02  5805.3  1031.5  5956.9 1036.99
    6019 1047.36  6081.8 1059.02  6885.1 1108.57    7072 1111.17  7182.2  1110.1
#Mann= 13 ,-1 , 0
  3235.1     .12       0  4018.3     .05       0  4476.2     .12       0
  4755.4     .07       0  4884.6     .04       0  5023.8     .07       0
  5281.9     .05       0  5412.5     .07       0  5491.5     .05       0
  5805.3     .12       0    6019     .05       0  6885.1     .07       0
    7072     .05       0
#XS Ineff= 2 , 0
       0                 5542.13       0 1048.13
Permanent Ineff=
       F       F
Bank Sta=4884.6,5023.8
XS Rating Curve= 0 ,0
Exp/Cntr=0.3,0.1

Type RM Length L Ch R = 1 ,1725728 ,2629,2629,2629
BEGIN DESCRIPTION:
Guadalupe River - 28
END DESCRIPTION:
XS GIS Cut Line= 3
      2145963.73     13867546.97       2144066.9     13866452.65
      2141805.31      13866258.1
#Sta/Elev= 30
  2265.5 1125.94  2317.8 1125.23  2341.6 1124.69  2565.2 1111.17    2677 1097.51
  2735.7  1089.2    2772 1076.97    2814 1075.35  2881.1 1068.75  3149.2 1043.45
  3235.9 1041.69  4577.7 1020.27  4808.6 1009.52  4878.8 1002.66    4919  990.87
    4939  979.78  4974.5  976.32  5039.4  979.32  5059.5  989.83  5195.5 1028.02
    5210 1036.77  5230.1 1038.47  5250.2 1061.06    5451 1071.58  5549.6 1077.29
  5656.1 1082.76  6232.6  1122.1  6409.8 1126.64  6634.7 1128.11  6725.3 1129.46
#Mann= 17 ,-1 , 0
  2265.5     .12       0  2317.8     .07       0  2341.6     .12       0
  2565.2     .05       0    2677     .12       0    2814     .07       0
  2881.1     .12       0  3149.2     .07       0  3235.9     .05       0
    4919     .04       0  5059.5    .035       0  5195.5     .07       0
    5451     .05       0  5549.6     .07       0  5656.1     .05       0
  6409.8     .07       0  6634.7     .12       0
Bank Sta=4919,5059.5
XS Rating Curve= 0 ,0
Exp/Cntr=0.3,0.1

Type RM Length L Ch R = 1 ,1723099 ,2044,2044,2044
BEGIN DESCRIPTION:
Guadalupe River - 27
END DESCRIPTION:
XS GIS Cut Line= 3
      2146109.66     13867425.39      2145598.95     13867157.88
      2145234.17     13864215.33
#Sta/Elev= 30
  3281.9 1122.08  3295.4 1121.68  3623.9 1107.43  3733.4 1094.19  3842.9 1078.48
  4197.7 1056.05  4346.2 1035.85  4375.2 1030.29  4486.1 1027.44  4808.5 1032.81
  4838.8  1026.2  4905.4  981.77  4910.5  983.17  4974.5  972.08  5017.4  972.08
  5060.4  977.14  5072.4  982.86    5131  992.81  5204.5  995.52  5352.7 1009.73
  5391.8 1017.95  5493.7 1021.34  5584.4 1034.78  5690.2 1038.95  5695.5 1039.03
  5789.9 1045.59  6249.5 1080.65  6352.9 1092.82  6610.4 1110.76  6823.5 1115.27
#Mann= 15 ,-1 , 0
  3281.9     .05       0  3295.4     .07       0  3623.9     .05       0
  3733.4     .12       0  3842.9     .07       0  4197.7     .12       0
  4346.2     .05       0  4910.5     .04       0  5072.4     .07       0
  5204.5     .07       0  5391.8     .12       0  5690.2     .05       0
  5695.5     .07       0  5789.9     .05       0  6352.9     .07       0
Bank Sta=4910.5,5072.4
XS Rating Curve= 0 ,0
Exp/Cntr=0.3,0.1

Type RM Length L Ch R = 1 ,1721055 ,3390,3390,3390
BEGIN DESCRIPTION:
Guadalupe River - 26
END DESCRIPTION:
XS GIS Cut Line= 3
      2147495.78     13866671.49      2147325.55     13865650.14
      2145623.25     13863850.56
#Sta/Elev= 30
  3236.2 1113.07  3424.6 1105.75  3739.5  1090.5  4004.7 1087.85  4441.9 1060.61
  4627.2 1050.63  4657.7 1047.85  4676.3  1033.8    4707 1009.12  4735.3 1000.22
  4848.6  981.01  4905.2  980.56  4976.8  971.47  5019.8  971.47  5067.9  981.05
  5152.8  995.97  5173.9 1022.27  5181.1 1023.27  5244.7 1019.51  5301.3 1024.89
  5633.8 1030.83  5697.3 1035.82  5803.7 1053.51  5940.6 1064.46  5978.2  1065.5
  6204.3  1077.5  6300.5 1084.57  6325.4 1086.01    6504 1108.06  6748.8 1119.22
#Mann= 12 ,-1 , 0
  3236.2     .12       0  3424.6     .05       0  4441.9     .12       0
  4627.2     .05       0  4676.3     .12       0  4905.2     .04       0
  5067.9     .12       0  5940.6     .07       0  5978.2     .05       0
  6204.3     .07       0  6300.5     .05       0  6325.4     .12       0
Bank Sta=4905.2,5067.9
XS Rating Curve= 0 ,0
Exp/Cntr=0.3,0.1

Type RM Length L Ch R = 1 ,1717665 ,2786,2786,2786
BEGIN DESCRIPTION:
Guadalupe River - 25
END DESCRIPTION:
XS GIS Cut Line= 2
      2148808.96     13866063.58      2149319.66     13862902.16
#Sta/Elev= 30
  2782.7 1101.18  3038.8 1095.34  3168.3  1088.2  3296.1 1066.64  3559.9 1033.73
  3642.3 1023.27    3774 1022.27  3898.7 1038.21  4104.6 1039.47  4260.2 1021.48
  4485.2 1023.77  4596.9 1019.38  4696.1 1011.16  4878.1  983.78  4932.5  968.72
    5062  971.72  5080.7  987.59  5107.7 1000.22  5121.2 1001.64  5131.3 1009.09
  5141.5 1029.27  5151.6 1038.99    5182 1055.23  5234.8 1073.07  5252.9 1102.31
  5433.9 1113.31  5645.7 1122.48  5761.9 1125.95  5866.7 1126.87  5985.1 1126.89
#Mann= 13 ,-1 , 0
  2782.7     .05       0  3038.8     .12       0  3296.1     .05       0
  3559.9     .12       0  3898.7     .05       0  4596.9     .12       0
  4696.1     .07       0  4878.1     .04       0  5080.7     .07       0
  5433.9     .08       0  5645.7     .12       0  5761.9     .05       0
  5866.7     .12       0
Bank Sta=4878.1,5080.7
XS Rating Curve= 0 ,0
Exp/Cntr=0.3,0.1

Type RM Length L Ch R = 1 ,1714879 ,1861,1861,1861
BEGIN DESCRIPTION:
Guadalupe River - 24
END DESCRIPTION:
XS GIS Cut Line= 2
      2151362.39     13866112.23       2151508.3     13863242.63
#Sta/Elev= 30
  3559.7 1135.61  3852.1  1129.9  4157.7 1123.03    4398 1099.67  4458.1 1080.46
  4495.2  1056.7  4558.2 1035.27  4578.2 1020.28  4709.5 1019.54  4838.6 1010.28
  4892.4   998.6  4928.7  981.86  4948.7  969.99  4974.2   966.8  5017.5   966.8
  5038.8  975.52  5108.9     977    5149  988.79    5189  993.19  5209.1 1003.23
  5259.1 1008.61  5279.1 1015.55  5369.3 1017.25  5467.7 1026.23  5619.6 1037.37
  5739.7 1062.48  5821.8 1069.26  5920.2  1076.5  6080.6 1083.03    6433 1088.61
#Mann= 10 ,-1 , 0
  3559.7     .07       0  3852.1     .12       0  4709.5      .1       0
  4928.7     .04       0  5038.8     .07       0  5467.7     .05       0
  5619.6     .07       0  5821.8     .12       0  5920.2     .05       0
  6080.6     .12       0
Bank Sta=4928.7,5038.8
XS Rating Curve= 0 ,0
Exp/Cntr=0.3,0.1

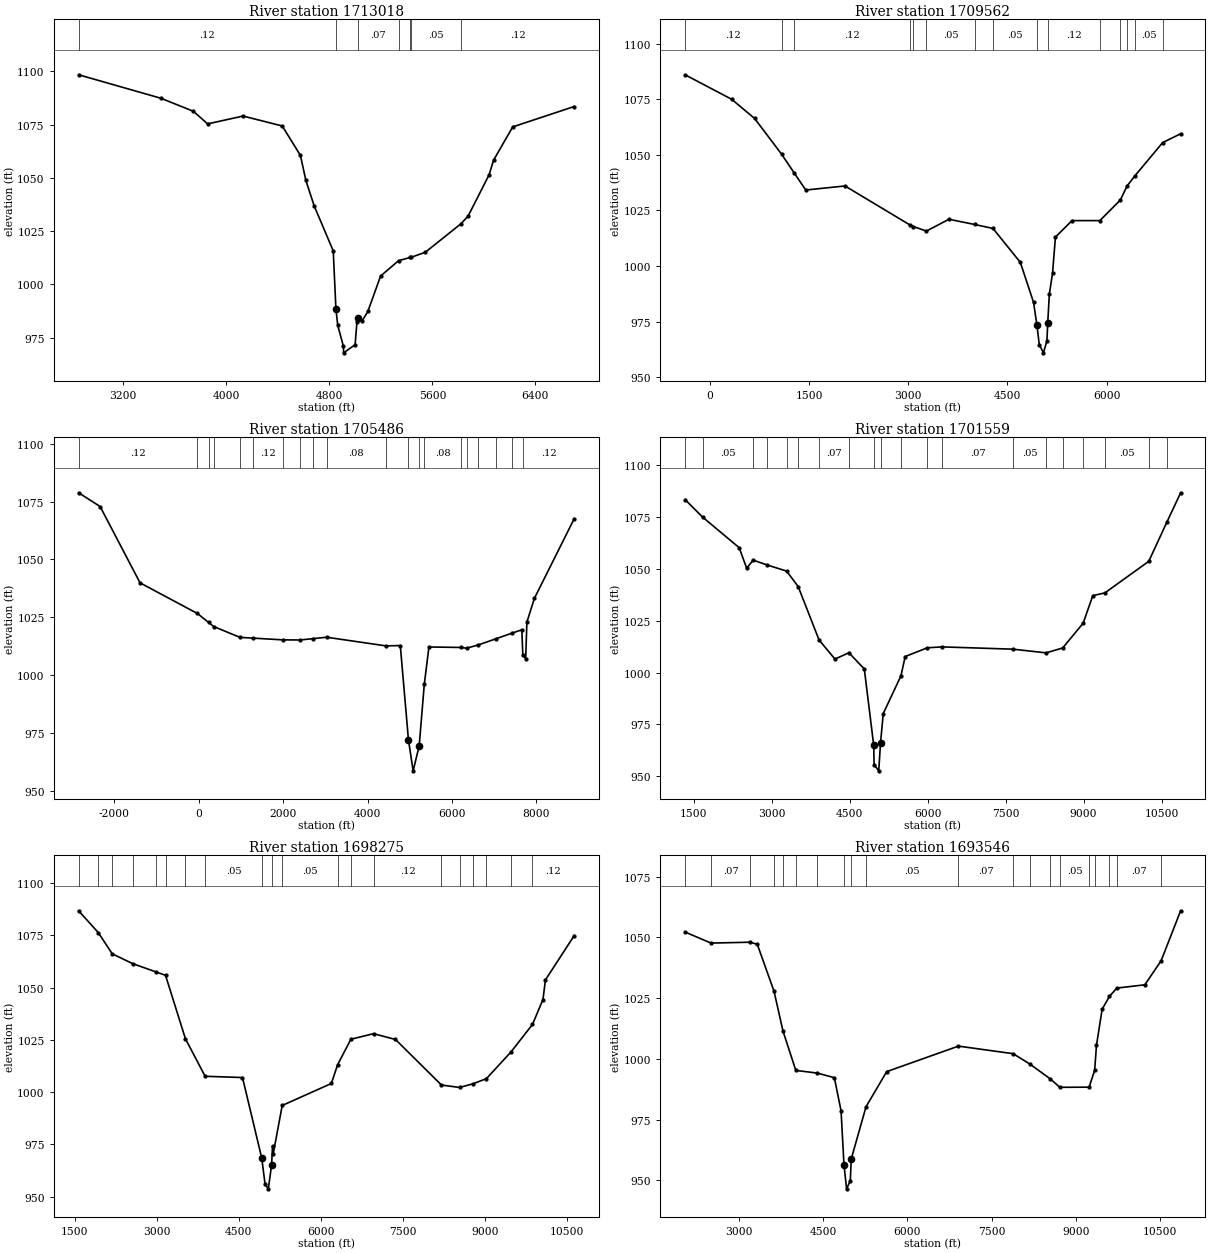
Type RM Length L Ch R = 1 ,1713018 ,3456,3456,3456
BEGIN DESCRIPTION:
Guadalupe River - 23
END DESCRIPTION:
XS GIS Cut Line= 3
      2153332.19     13866063.53      2153818.54     13865139.46
      2151776.72     13863219.17
#Sta/Elev= 30
  2853.6 1098.43  3491.7 1087.42  3744.7 1081.28    3855 1075.36  4129.9 1079.05
  4434.2 1074.39  4575.4 1060.58  4617.8 1048.82  4681.8 1036.94  4830.3 1015.72
  4851.3  988.21  4865.5  980.73  4909.6  970.85  4910.6  967.85  5000.2  971.66
  5014.4  982.52  5021.2  984.06  5056.4  983.01  5098.9  987.29  5198.1 1003.93
  5337.6 1011.13  5429.4 1012.67  5434.2  1012.7  5544.8 1015.07  5823.9 1028.57
  5877.4 1032.08  6040.1 1051.44  6075.2 1058.34  6223.7 1073.96  6700.8 1083.52
#Mann= 7 ,-1 , 0
  2853.6     .12       0  4851.3     .04       0  5021.2     .07       0
  5337.6     .07       0  5429.4     .12       0  5434.2     .05       0
  5823.9     .12       0
Bank Sta=4851.3,5021.2
XS Rating Curve= 0 ,0
Exp/Cntr=0.3,0.1

Type RM Length L Ch R = 1 ,1709562 ,4076,4076,4076
BEGIN DESCRIPTION:
Guadalupe River - 22
END DESCRIPTION:
XS GIS Cut Line= 3
      2153818.52     13865917.68      2155374.92     13862464.44
      2152335.99     13860349.35
#Sta/Elev= 30
  -372.3 1086.02   332.1 1074.99     678 1066.38  1085.8 1050.32  1277.5 1041.83
  1451.3 1034.18  2044.9    1036  3020.7 1018.56  3078.4 1017.77  3275.2 1015.71
  3616.1 1021.03  4003.6 1018.68  4281.3  1016.9  4694.7 1001.65  4894.7  983.65
  4945.3  973.42  4981.1  964.68  5043.7  960.94  5096.7  966.28  5109.4  974.51
    5133  987.21    5182  996.89  5225.5    1013  5475.9 1020.42  5896.9 1020.42
  6207.3 1029.71  6309.1 1036.04  6430.1 1040.68  6846.5 1055.52    7118 1059.49
#Mann= 15 ,-1 , 0
  -372.3     .12       0  1085.8     .05       0  1277.5     .12       0
  3020.7     .05       0  3078.4     .12       0  3275.2     .05       0
  4003.6     .07       0  4281.3     .05       0  4945.3     .04       0
  5109.4     .12       0  5896.9     .12       0  6207.3     .05       0
  6309.1     .12       0  6430.1     .05       0  6846.5     .12       0
Bank Sta=4945.3,5109.4
XS Rating Curve= 0 ,0
Exp/Cntr=0.3,0.1

Type RM Length L Ch R = 1 ,1705486 ,3927,3927,3927
BEGIN DESCRIPTION:
Guadalupe River - 21
END DESCRIPTION:
XS GIS Cut Line= 5
      2154061.73       13865869.      2155642.42     13862513.08
      2156493.56     13859667.84      2156031.51     13857163.05
      2154257.39     13855388.93
#Sta/Elev= 30
 -2841.1 1078.78 -2331.3 1072.82 -1386.6 1039.86   -29.7 1026.63   235.2 1022.78
   359.4 1020.97   979.8  1016.3  1285.1 1015.98  1997.5 1015.22  2404.5 1015.18
  2709.8 1015.75  3033.7 1016.36    4433 1012.63  4776.7 1012.76  4969.9  971.96
  5080.8  958.63  5224.1  969.44    5345  996.06  5454.7 1012.15  6216.9 1011.94
  6344.6 1011.63  6614.3 1012.97  7044.8 1015.71  7418.3 1018.09  7654.3 1019.59
  7678.2 1008.73  7746.2  1007.1  7774.5 1022.87  7951.2 1033.13  8894.3 1067.56
#Mann= 20 ,-1 , 0
 -2841.1     .12       0   -29.7     .07       0   235.2     .05       0
   359.4     .07       0   979.8     .07       0  1285.1     .12       0
  1997.5     .05       0  2404.5     .07       0  2709.8     .05       0
  3033.7     .08       0    4433     .08       0  4969.9     .04       0
  5224.1     .08       0    5345     .08       0  6216.9      .1       0
  6344.6     .08       0  6614.3     .05       0  7044.8     .07       0
  7418.3     .12       0  7678.2     .12       0
Bank Sta=4969.9,5224.1
XS Rating Curve= 0 ,0
Exp/Cntr=0.3,0.1

Type RM Length L Ch R = 1 ,1701559 ,3284,3284,3284
BEGIN DESCRIPTION:
Guadalupe River - 20
END DESCRIPTION:
XS GIS Cut Line= 4
       2159703.6     13862902.15      2160019.71     13862561.72
      2159290.17     13859765.11      2162499.52     13854489.13
#Sta/Elev= 30
  1335.6 1083.19  1670.9 1074.82  2375.5 1060.06  2520.2 1050.18  2644.4 1054.09
  2906.7  1051.8  3288.1 1048.79  3510.2 1041.37    3912 1015.65  4217.9 1006.45
  4485.5 1009.51  4782.3  1001.7  4962.5  965.07  4971.1  955.68  5059.9  952.68
  5094.2  966.13  5146.5  980.25  5486.1  998.35  5568.4 1007.69  5993.9 1011.89
  6277.6 1012.33  7639.5 1011.23  8279.4 1009.46  8597.4 1011.82  8991.3 1023.75
  9176.4 1036.99  9408.9 1038.31 10252.3 1053.49 10599.3 1072.27 10865.8 1086.49
#Mann= 20 ,-1 , 0
  1335.6     .07       0  1670.9     .05       0  2644.4     .07       0
  2906.7     .12       0  3288.1     .07       0  3510.2     .05       0
    3912     .07       0  4485.5     .05       0  4962.5     .04       0
  5094.2     .12       0  5486.1     .05       0  5993.9     .05       0
  6277.6     .07       0  7639.5     .05       0  8279.4     .07       0
  8597.4     .07       0  8991.3     .12       0  9408.9     .05       0
 10252.3     .07       0 10599.3     .05       0
Bank Sta=4962.5,5094.2
XS Rating Curve= 0 ,0
Exp/Cntr=0.3,0.1

Type RM Length L Ch R = 1 ,1698275 ,4729,4729,4729
BEGIN DESCRIPTION:
Guadalupe River - 19
END DESCRIPTION:
XS GIS Cut Line= 4
       2159703.6     13863048.07      2161624.72     13861783.53
      2162767.69     13858622.15      2165685.86     13856895.56
#Sta/Elev= 30
    1574 1086.73  1935.6 1076.21    2188 1066.14  2561.1 1061.45  2990.1 1057.46
  3161.2 1055.87  3525.6 1025.48  3884.8 1007.58  4567.4 1006.98  4919.3  968.42
  4980.1  955.89  5039.3  953.75  5097.9  964.92  5116.5  974.36  5128.6  970.47
    5293  993.63  6190.5 1004.13  6304.6 1013.07  6547.2 1025.29  6961.1 1027.95
  7361.9 1025.19  8202.4 1003.38  8533.1 1002.24  8786.3 1004.06  9024.6 1006.48
  9475.7 1019.33  9864.5 1032.37   10056 1044.26 10101.8 1053.69 10626.3 1074.83
#Mann= 20 ,-1 , 0
    1574     .05       0  1935.6     .07       0    2188     .05       0
  2561.1     .05       0  2990.1     .05       0  3161.2     .07       0
  3525.6     .05       0  3884.8     .05       0  4919.3     .04       0
  5097.9     .12       0    5293     .05       0  6304.6     .07       0
  6547.2     .12       0  6961.1     .12       0  8202.4     .12       0
  8533.1     .05       0  8786.3     .07       0  9024.6     .05       0
  9475.7     .07       0  9864.5     .12       0
Bank Sta=4919.3,5097.9
XS Rating Curve= 0 ,0
Exp/Cntr=0.3,0.1

Type RM Length L Ch R = 1 ,1693546 ,3605,3605,3605
BEGIN DESCRIPTION:
Guadalupe River - 18
END DESCRIPTION:
XS GIS Cut Line= 4
      2162500.19     13865090.81      2163545.87     13863534.45
      2165491.34     13862610.35      2165904.75     13857843.96
#Sta/Elev= 30
  2049.4 1052.22  2509.4 1047.68  3203.3 1048.03  3333.4 1047.18  3632.1 1027.77
  3789.7 1011.53  4018.5  995.28  4397.9  994.19  4703.9   992.3  4823.1  978.67
  4875.5  956.29  4921.5  946.55  4987.7  949.92  5004.9  958.88  5267.6  980.36
    5635  994.78  6910.2 1005.28  7884.4 1002.16  8180.5   997.9    8545  991.78
  8712.9  988.33  9234.5  988.39    9333  995.27  9365.9 1005.62  9466.2 1020.44
  9595.9 1025.73    9727 1029.16 10226.5 1030.51   10515  1040.4 10862.5 1060.97
#Mann= 20 ,-1 , 0
  2049.4     .07       0  2509.4     .07       0  3203.3     .12       0
  3632.1     .05       0  3789.7     .12       0  4018.5     .05       0
  4397.9     .07       0  4875.5     .04       0  5004.9     .12       0
  5267.6     .05       0  6910.2     .07       0  7884.4     .05       0
  8180.5     .07       0    8545     .12       0  8712.9     .05       0
  9234.5     .07       0    9333     .05       0  9595.9     .12       0
    9727     .07       0   10515     .12       0
Bank Sta=4875.5,5004.9
XS Rating Curve= 0 ,0
Exp/Cntr=0.3,0.1

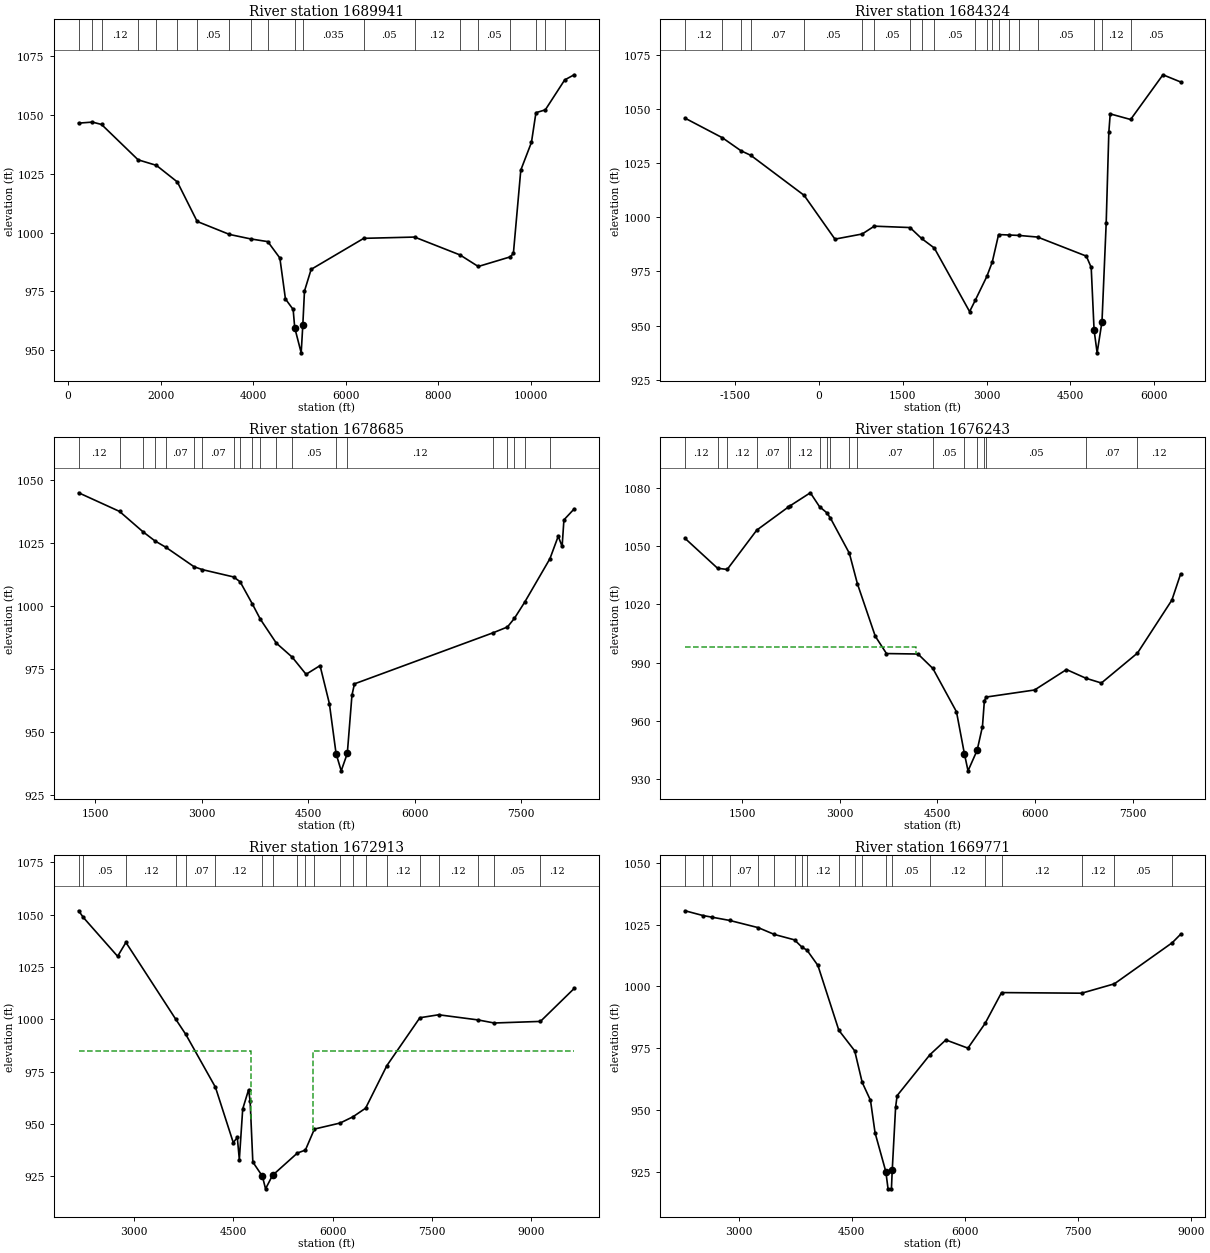
Type RM Length L Ch R = 1 ,1689941 ,5617,5617,5617
BEGIN DESCRIPTION:
Guadalupe River - 17
END DESCRIPTION:
XS GIS Cut Line= 4
      2163521.51     13864726.05      2167242.26     13864555.82
      2165856.11     13861710.58      2166050.66      13857892.6
#Sta/Elev= 30
   229.5 1046.58   527.3 1047.02   724.8 1046.01  1515.1 1030.96  1910.2  1028.6
  2363.9 1021.52  2791.8 1004.71  3490.7  999.18  3948.9  997.27  4318.5  996.12
  4579.7  989.14  4700.3   971.7  4867.1  967.23  4900.8  959.46  5040.7  948.76
  5075.5  960.47  5111.9  975.07  5255.8  984.31  6393.2  997.52  7491.6  998.06
    8474  990.45  8868.6  985.53  9557.2  989.61  9627.9  991.07  9788.1 1026.58
 10018.4 1038.39 10115.6 1051.02 10318.2 1052.24 10737.5 1064.99   10942 1067.17
#Mann= 20 ,-1 , 0
   229.5     .12       0   527.3     .07       0   724.8     .12       0
  1515.1     .07       0  1910.2     .05       0  2363.9     .07       0
  2791.8     .05       0  3490.7     .07       0  3948.9     .05       0
  4318.5     .07       0  4900.8     .04       0  5075.5    .035       0
  6393.2     .05       0  7491.6     .12       0    8474     .07       0
  8868.6     .05       0  9557.2     .05       0 10115.6     .07       0
 10318.2     .05       0 10737.5     .05       0
Bank Sta=4900.8,5075.5
XS Rating Curve= 0 ,0
Exp/Cntr=0.3,0.1

Type RM Length L Ch R = 1 ,1684324 ,5639,5639,5639
BEGIN DESCRIPTION:
Guadalupe River - 16
END DESCRIPTION:
XS GIS Cut Line= 4
      2163813.42     13864847.64      2167242.26     13864993.55
      2169795.68     13862926.49      2171887.07     13862391.49
#Sta/Elev= 30
 -2399.7 1045.71 -1730.7 1036.67 -1398.3 1030.68 -1222.4 1028.57  -268.1 1010.13
   284.3  989.92   772.6  992.29   988.9   995.9    1629  995.26  1834.7  990.25
  2063.9  985.82  2696.3  956.48  2800.2  961.84  3004.4  972.68  3101.6   979.3
  3215.4  992.03    3403  991.82  3577.2  991.63  3914.3  990.87    4787  982.08
  4874.2  976.87  4925.8  948.02  4980.4  937.46  5067.5  951.86  5142.5  997.18
    5190 1039.21  5214.8  1047.7  5580.3 1045.11  6159.3 1065.74  6476.2 1062.42
#Mann= 20 ,-1 , 0
 -2399.7     .12       0 -1730.7     .05       0 -1398.3     .12       0
 -1222.4     .07       0  -268.1     .05       0   772.6     .07       0
   988.9     .05       0    1629     .07       0  1834.7     .07       0
  2063.9     .05       0  2800.2     .05       0  3004.4     .07       0
  3101.6     .12       0  3215.4     .05       0    3403     .05       0
  3577.2     .05       0  3914.3     .05       0  4925.8     .04       0
  5067.5     .12       0  5580.3     .05       0
Bank Sta=4925.8,5067.5
XS Rating Curve= 0 ,0
Exp/Cntr=0.3,0.1

Type RM Length L Ch R = 1 ,1678685 ,2442,2442,2442
BEGIN DESCRIPTION:
Guadalupe River - 15
END DESCRIPTION:
XS GIS Cut Line= 4
      2163740.46      13864920.6      2165564.29     13865309.69
      2168239.31     13866963.33      2170209.06     13866817.43
#Sta/Elev= 30
  1263.3  1045.1  1839.9 1037.69  2170.4  1029.6  2340.3 1025.94  2491.8 1023.46
  2889.7 1015.72  3006.7 1014.56  3450.2 1011.63  3540.2  1009.7  3708.6 1001.09
  3824.7  994.85  4049.7  985.35  4273.5  979.77  4469.2  972.95  4666.2  976.41
  4797.4  961.34    4892  941.44  4964.3  934.58  5050.4  941.49  5115.9  964.64
  5151.1  969.15  7109.7   989.5  7307.8  991.76  7406.8  995.23  7550.8 1001.62
  7906.5  1018.9  8023.5 1027.83  8078.3 1023.76  8103.7 1034.33  8248.2 1038.69
#Mann= 20 ,-1 , 0
  1263.3     .12       0  1839.9     .12       0  2170.4     .07       0
  2340.3     .12       0  2491.8     .07       0  2889.7     .12       0
  3006.7     .07       0  3450.2     .05       0  3540.2     .07       0
  3708.6     .05       0  3824.7     .07       0  4049.7     .07       0
  4273.5     .05       0    4892     .04       0  5050.4     .12       0
  7109.7     .07       0  7307.8     .05       0  7406.8     .07       0
  7550.8     .12       0  7906.5     .12       0
Bank Sta=4892,5050.4
XS Rating Curve= 0 ,0
Exp/Cntr=0.3,0.1

Type RM Length L Ch R = 1 ,1676243 ,3330,3330,3330
BEGIN DESCRIPTION:
Guadalupe River - 14
END DESCRIPTION:
XS GIS Cut Line= 4
       2163886.3     13870732.71      2165272.47      13868908.8
      2168506.81     13867838.79      2170257.75      13867060.6
#Sta/Elev= 30
   623.4 1053.95    1122 1038.63  1270.1 1037.99  1724.4 1058.22  2205.7    1070
  2228.2 1070.54  2547.6 1077.43  2688.8 1070.28  2799.5 1067.19  2857.2 1064.36
  3147.3 1046.31  3270.6 1030.66  3545.4 1003.65  3717.5  994.74    4202   994.5
  4430.2  987.07    4793   964.8  4914.6  943.23  4970.6  934.42  5110.2  944.97
  5192.1   957.2  5221.3  970.32  5248.1  972.36  5992.6     976  6483.2  986.51
    6782  982.04  7019.4  979.59  7574.1     995  8102.8 1022.25  8237.1  1035.7
#Mann= 18 ,-1 , 0
   623.4     .12       0    1122     .05       0  1270.1     .12       0
  1724.4     .07       0  2205.7     .05       0  2228.2     .12       0
  2688.8     .07       0  2799.5     .05       0  2857.2     .07       0
  3147.3     .05       0  3270.6     .07       0  4430.2     .05       0
  4914.6     .04       0  5110.2     .05       0  5221.3     .12       0
  5248.1     .05       0    6782     .07       0  7574.1     .12       0
#XS Ineff= 2 , 0
       0 4165.72  998.23               0
Permanent Ineff=
       F       F
Bank Sta=4914.6,5110.2
XS Rating Curve= 0 ,0
Exp/Cntr=0.3,0.1

Type RM Length L Ch R = 1 ,1672913 ,3142,3142,3142
BEGIN DESCRIPTION:
Guadalupe River - 13
END DESCRIPTION:
XS GIS Cut Line= 4
      2164542.93     13871146.08      2166585.66     13870343.58
      2169382.27     13869784.26      2170014.53     13867425.43
#Sta/Elev= 30
  2161.6 1051.91  2233.2  1048.7    2751 1030.15  2876.2  1036.8  3626.3 1000.25
  3781.3  992.85  4229.1  967.62  4498.4  941.18  4559.6  943.65  4590.2   933.1
  4641.2  957.23  4729.7   966.4  4753.4  961.06  4794.2  931.91  4938.7  925.12
  4986.3   919.1  5091.7  925.54  5467.7   936.2  5588.5   937.6  5724.8  947.65
  6113.6  950.53  6306.9   953.5  6498.5  957.62  6819.3  977.93  7318.6 1000.82
  7601.7 1002.24    8195  999.79  8441.5  998.31  9140.7  999.07  9650.4  1014.8
#Mann= 20 ,-1 , 0
  2161.6     .12       0  2233.2     .05       0  2876.2     .12       0
  3626.3     .12       0  3781.3     .07       0  4229.1     .12       0
  4938.7     .04       0  5091.7     .07       0  5467.7     .07       0
  5588.5     .05       0  5724.8     .07       0  6113.6     .12       0
  6306.9     .05       0  6498.5     .07       0  6819.3     .12       0
  7318.6     .05       0  7601.7     .12       0    8195     .12       0
  8441.5     .05       0  9140.7     .12       0
#XS Ineff= 2 , 0
       0  4766.3  984.81 5709.89       0  984.98
Permanent Ineff=
       F       F
Bank Sta=4938.7,5091.7
XS Rating Curve= 0 ,0
Exp/Cntr=0.3,0.1

Type RM Length L Ch R = 1 ,1669771 ,4139,4139,4139
BEGIN DESCRIPTION:
Guadalupe River - 12
END DESCRIPTION:
XS GIS Cut Line= 4
      2168774.34     13873140.17      2169965.91     13872459.27
       2169552.5     13869468.12      2170159.75     13867379.18
#Sta/Elev= 30
  2290.2 1030.56    2526 1028.64    2650 1027.95    2881 1026.65  3260.8 1023.72
  3474.1 1020.97  3740.2 1018.79  3839.9  1015.8  3904.8 1014.66  4050.5 1008.42
  4327.7   982.2    4538  973.87  4637.1  961.12  4747.1  953.84  4807.7   940.7
  4950.7  924.96  4979.9  918.02  5024.6  918.02  5035.8  925.76  5080.2  951.14
  5100.4  955.75  5535.3  972.32  5746.2  978.29  6038.6  974.96  6265.6  984.95
  6484.1  997.45  7545.5   997.2  7978.9 1000.99    8747 1017.65  8857.6 1021.06
#Mann= 20 ,-1 , 0
  2290.2     .05       0    2526     .07       0    2650     .05       0
    2881     .07       0  3260.8     .07       0  3474.1     .05       0
  3740.2     .12       0  3839.9     .07       0  3904.8     .12       0
  4327.7     .05       0    4538     .12       0  4637.1     .07       0
  4950.7     .04       0  5035.8     .05       0  5535.3     .12       0
  6265.6     .05       0  6484.1     .12       0  7545.5     .12       0
  7978.9     .05       0    8747     .12       0
Bank Sta=4950.7,5035.8
XS Rating Curve= 0 ,0
Exp/Cntr=0.3,0.1

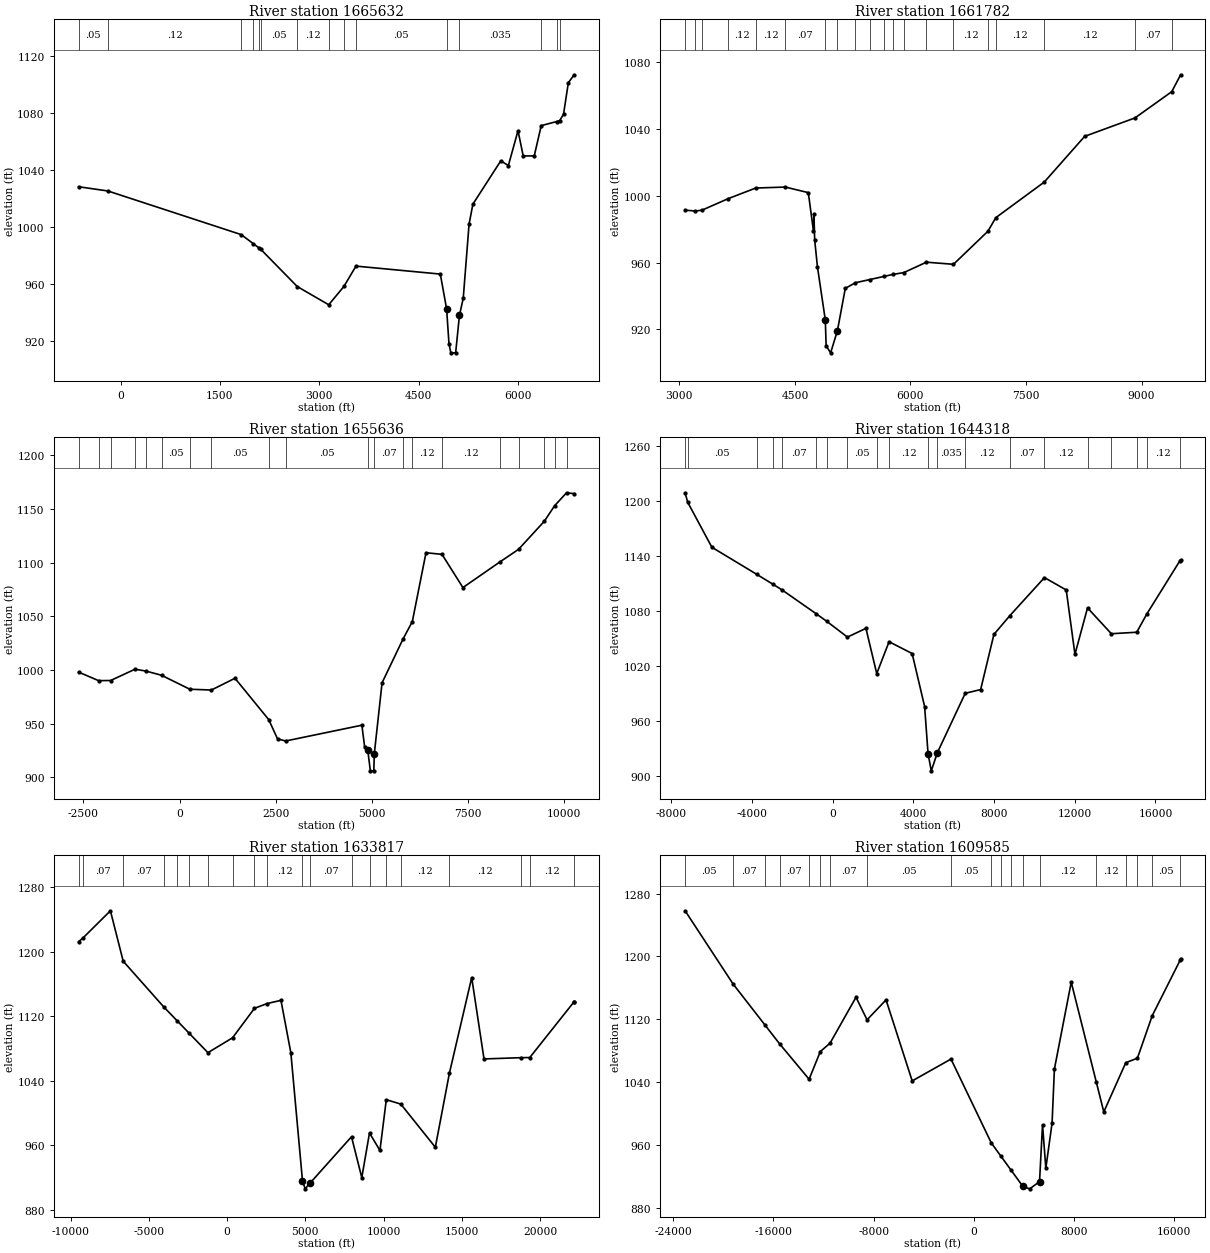
Type RM Length L Ch R = 1 ,1665632 ,3850,3850,3850
BEGIN DESCRIPTION:
Guadalupe River - 11
END DESCRIPTION:
XS GIS Cut Line= 3
      2168774.31     13873237.46      2171327.73      13872094.5
      2173856.85     13868154.91
#Sta/Elev= 30
  -632.1 1028.14  -190.2 1025.16  1822.2  994.51  2004.1  988.16  2086.7  985.29
  2113.6  984.35  2667.2  958.06  3142.6  945.25  3371.5   958.1  3553.8   972.4
  4826.7   966.8  4921.8  942.36  4957.4  917.91  4985.3  911.49  5058.1  911.49
  5115.4  937.81  5172.8  949.85  5260.7 1001.89  5318.2 1015.89    5739 1046.32
  5853.9 1043.02  5999.3 1067.51  6077.9 1049.79  6244.4 1049.78  6349.8 1071.07
    6585 1073.94  6627.5 1074.51  6686.3 1079.03    6759  1101.2    6847 1106.77
#Mann= 15 ,-1 , 0
  -632.1     .05       0  -190.2     .12       0  1822.2     .05       0
  2004.1     .07       0  2086.7     .12       0  2113.6     .05       0
  2667.2     .12       0  3142.6     .07       0  3371.5     .12       0
  3553.8     .05       0  4921.8     .04       0  5115.4    .035       0
  6349.8     .07       0    6585     .05       0  6627.5     .07       0
Bank Sta=4921.8,5115.4
XS Rating Curve= 0 ,0
Exp/Cntr=0.3,0.1

Type RM Length L Ch R = 1 ,1661782 ,6146,6146,6146
BEGIN DESCRIPTION:
Guadalupe River - 10
END DESCRIPTION:
XS GIS Cut Line= 4
      2171473.65     13872459.28      2172762.52     13873261.78
      2173881.16     13871121.77      2174634.81     13868739.26
#Sta/Elev= 30
  3075.1   991.3  3209.4  990.78  3295.3  991.31  3637.1  998.23  3991.9 1004.53
  4375.6 1005.11  4674.3 1001.78  4740.6  979.06  4747.7  988.93    4757   973.5
  4792.9  957.47  4895.1  925.59  4905.7  910.22  4964.1  906.02  5052.4  919.33
  5154.4  944.55  5285.8  947.92  5469.3  949.79  5656.8   951.7  5778.5  952.94
  5912.9  953.97  6207.5   960.2  6558.6  958.94  7005.7   978.7    7108  986.81
  7736.9 1008.09  8261.2 1035.41  8914.7 1046.43  9391.8 1062.13    9507 1072.22
#Mann= 20 ,-1 , 0
  3075.1     .08       0  3209.4     .08       0  3295.3     .07       0
  3637.1     .12       0  3991.9     .12       0  4375.6     .07       0
  4895.1     .04       0  5052.4     .07       0  5285.8     .05       0
  5469.3     .07       0  5656.8     .05       0  5778.5     .07       0
  5912.9     .07       0  6207.5     .07       0  6558.6     .12       0
  7005.7     .07       0    7108     .12       0  7736.9     .12       0
  8914.7     .07       0  9391.8     .12       0
Bank Sta=4895.1,5052.4
XS Rating Curve= 0 ,0
Exp/Cntr=0.3,0.1

Type RM Length L Ch R = 1 ,1655636 ,11318,11318,11318
BEGIN DESCRIPTION:
Guadalupe River - 9
END DESCRIPTION:
XS GIS Cut Line= 5
      2171219.27     13872511.37      2173026.93     13873524.76
      2175546.67      13873196.1      2178093.79     13869580.83
      2176122.79     13866268.46
#Sta/Elev= 30
 -2625.7  998.02 -2105.8  990.07 -1792.8   990.2 -1158.9 1000.74  -868.9  998.96
  -469.3  995.07   267.2  982.07   827.8  981.34  1441.5  992.29  2318.9  953.76
  2547.4  935.85  2759.6  933.84  4742.2  948.56  4814.8  928.17  4893.7  925.78
  4962.5  906.02  5052.1  906.02  5066.1  922.08  5267.4  988.07  5809.2  1028.6
  6054.4 1045.12  6410.2 1109.26  6826.2 1107.78  7370.6 1076.81    8325  1100.5
  8817.3 1112.43  9489.6 1138.67  9752.9 1152.95 10065.9 1165.15 10264.6 1164.32
#Mann= 20 ,-1 , 0
 -2625.7     .12       0 -2105.8     .08       0 -1792.8     .12       0
 -1158.9     .07       0  -868.9     .12       0  -469.3     .05       0
   267.2     .05       0   827.8     .05       0  2318.9     .12       0
  2759.6     .05       0  4893.7     .04       0  5066.1     .07       0
  5809.2     .07       0  6054.4     .12       0  6826.2     .12       0
    8325     .07       0  8817.3     .07       0  9489.6     .07       0
  9752.9     .12       0 10065.9     .07       0
Bank Sta=4893.7,5066.1
XS Rating Curve= 0 ,0
Exp/Cntr=0.3,0.1

Type RM Length L Ch R = 1 ,1644318 ,10501,10501,10501
BEGIN DESCRIPTION:
Guadalupe River - 8
END DESCRIPTION:
XS GIS Cut Line= 4
      2165265.52     13879718.41      2176839.19     13877248.66
      2179495.44     13872717.41      2177578.72     13865481.64
#Sta/Elev= 30
 -7324.9 1208.89 -7194.4 1198.51 -5996.2 1149.52 -3762.6 1119.92 -2973.5 1109.31
   -2542 1103.45  -829.1 1077.18  -301.3 1068.88   725.4 1051.69    1642 1061.24
  2177.8 1011.94  2788.8 1046.66  3932.8 1033.81  4552.3  976.03  4722.2  924.71
  4882.9  906.02  5187.5  925.97    6566   990.5  7330.3  994.53  7988.2  1054.6
  8763.4 1074.67 10494.2 1116.51 11574.4 1103.02 12006.5  1032.9   12630 1083.53
 13811.3 1055.36   15070 1056.99 15578.2 1077.15 17203.1 1134.56 17247.1 1135.64
#Mann= 20 ,-1 , 0
 -7324.9     .08       0 -7194.4     .05       0 -3762.6     .07       0
 -2973.5     .05       0   -2542     .07       0  -829.1     .05       0
  -301.3     .12       0   725.4     .05       0  2177.8     .12       0
  2788.8     .12       0  4722.2     .04       0  5187.5    .035       0
    6566     .12       0  8763.4     .07       0 10494.2     .12       0
   12630     .12       0 13811.3     .12       0   15070     .07       0
 15578.2     .12       0 17203.1     .07       0
Bank Sta=4722.2,5187.5
XS Rating Curve= 0 ,0
Exp/Cntr=0.3,0.1

Type RM Length L Ch R = 1 ,1633817 ,24232,24232,24232
BEGIN DESCRIPTION:
Guadalupe River - 7
END DESCRIPTION:
XS GIS Cut Line= 6
      2181178.18     13894768.59      2183389.81      13884763.6
      2181072.87     13883341.84      2180858.46     13879086.49
      2180979.93     13871190.82      2178247.11     13865239.33
#Sta/Elev= 30
 -9485.4 1212.39   -9210 1216.91 -7453.9 1250.65 -6636.8 1188.14 -4032.6 1131.23
 -3169.1  1113.9 -2448.1 1099.42 -1221.8  1074.8   350.8 1093.21  1754.3 1129.79
  2562.2 1135.67  3446.2 1139.65  4077.1 1074.74  4820.5   916.2  4991.4  906.02
  5308.1  913.18  7954.5   970.6  8611.8  919.96  9104.8  975.25    9772  953.57
 10178.6 1016.53 11106.7 1011.02 13312.4  957.57 14210.6 1049.24 15636.9 1167.85
 16423.3 1067.01 18770.1 1068.57   19348 1068.75 22180.6 1137.91 22185.8 1138.09
#Mann= 20 ,-1 , 0
 -9485.4     .05       0   -9210     .07       0 -6636.8     .07       0
 -4032.6     .12       0 -3169.1     .07       0 -2448.1     .07       0
 -1221.8     .05       0   350.8     .07       0  1754.3     .07       0
  2562.2     .12       0  4820.5     .04       0  5308.1     .07       0
  7954.5     .05       0  9104.8     .12       0 10178.6     .05       0
 11106.7     .12       0 14210.6     .12       0 18770.1     .07       0
   19348     .12       0 22180.6     .07       0
Bank Sta=4820.5,5308.1
XS Rating Curve= 0 ,0
Exp/Cntr=0.3,0.1

Type RM Length L Ch R = 1 ,1609585 ,20890,20890,20890
BEGIN DESCRIPTION:
Guadalupe River - 6
END DESCRIPTION:
XS GIS Cut Line= 6
      2181411.34     13895864.21      2183705.76     13884605.62
      2188866.22     13876759.61      2187432.35     13874150.36
      2181230.84     13871072.57      2177565.13     13863145.48
#Sta/Elev= 30
-23049.7 1258.09-19220.4 1164.88-16645.9 1112.03-15512.8 1088.77-13153.7 1043.58
-12255.7 1078.89-11484.7 1089.39 -9411.5 1147.97 -8527.5 1119.26 -7012.5 1144.62
 -4925.6 1041.44 -1829.1 1069.26  1385.5  962.49  2172.7  945.21  2947.5   928.2
  3912.7  907.01    4454  904.01  5237.4  913.19  5476.9  985.53  5739.8  930.22
  6238.9  987.87  6423.8  1056.5  7767.5 1167.17  9767.8 1039.99   10366 1001.96
 12120.1 1064.65 13048.2 1070.36 14235.2 1124.65 16454.3 1194.97 16498.7 1197.12
#Mann= 19 ,-1 , 0
-23049.7     .05       0-19220.4     .07       0-16645.9     .07       0
-15512.8     .07       0-13153.7     .12       0-12255.7     .07       0
-11484.7     .07       0 -8527.5     .05       0 -1829.1     .05       0
  1385.5     .07       0  2172.7     .07       0  2947.5     .07       0
  3912.7     .04       0  5237.4     .12       0  9767.8     .12       0
 12120.1     .05       0 13048.2     .05       0 14235.2     .05       0
 16454.3     .12       0
Bank Sta=3912.7,5237.4
XS Rating Curve= 0 ,0
Exp/Cntr=0.3,0.1

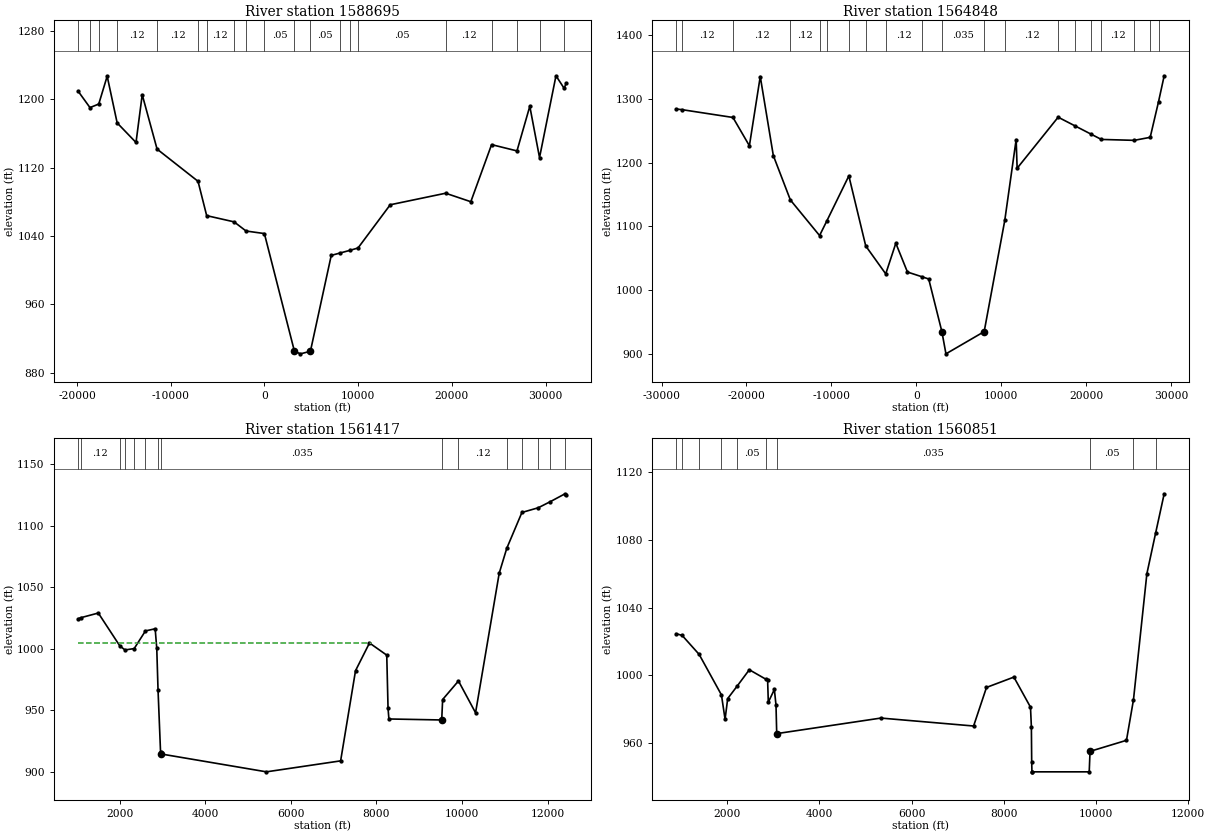
Type RM Length L Ch R = 1 ,1588695 ,23847,23847,23847
BEGIN DESCRIPTION:
Guadalupe River - 5
END DESCRIPTION:
XS GIS Cut Line= 6
      2192609.24     13897947.59      2199380.08     13886706.26
      2199175.69     13871318.44      2198485.38     13870244.62
      2199214.04      13869324.2      2184297.77     13854479.84
#Sta/Elev= 30
-19865.9 1209.09-18615.2 1190.11-17678.4 1194.27  -16779 1226.84-15714.6 1172.19
  -13703 1149.32-13040.8 1205.18-11455.6 1141.58 -7088.8 1103.97 -6164.2 1063.81
 -3242.4 1056.55 -1963.3 1045.84    -7.3 1042.86  3198.1  905.27  3843.3  902.27
  4903.2  905.27  7126.2 1017.35  8021.2 1019.99  9134.7 1023.29  9982.9 1026.01
 13416.7 1076.51 19329.5 1090.02 22015.2 1080.08 24230.7 1146.83 26940.7 1139.48
 28308.5 1191.63 29346.1 1131.67 31101.5  1227.3 31970.3 1212.64 32185.1 1218.43
#Mann= 20 ,-1 , 0
-19865.9     .07       0-18615.2     .07       0-17678.4     .05       0
-15714.6     .12       0-11455.6     .12       0 -7088.8     .05       0
 -6164.2     .12       0 -3242.4     .12       0 -1963.3     .05       0
    -7.3     .05       0  3198.1     .04       0  4903.2     .05       0
  8021.2     .08       0  9134.7     .05       0  9982.9     .05       0
 19329.5     .12       0 24230.7     .12       0 26940.7     .05       0
 29346.1     .05       0 31970.3     .05       0
Bank Sta=3198.1,4903.2
XS Rating Curve= 0 ,0
Exp/Cntr=0.3,0.1

Type RM Length L Ch R = 1 ,1564848 ,3431,3431,3431
BEGIN DESCRIPTION:
Guadalupe River - 4
END DESCRIPTION:
XS GIS Cut Line= 6
      2228860.59     13886660.14      2227265.61     13878630.18
      2218431.65     13871082.32      2220728.81       13866678.
      2216829.42     13857412.41      2201383.56     13850461.69
#Sta/Elev= 30
-28264.1 1283.68-27639.9 1282.87-21589.2 1270.54-19652.5 1226.21-18373.2 1334.71
-16832.4 1210.83-14824.6 1141.31-11384.7 1085.56-10522.6 1108.66   -7936 1179.01
 -5945.7 1069.29 -3588.7 1025.54 -2401.3 1073.53   -1032 1028.43   735.2 1020.77
    1474 1017.55    3024  935.17  3504.1  900.29  8007.7  935.09 10433.6 1109.17
 11775.8 1235.98 11890.9 1190.97 16723.7 1270.96 18732.2  1257.2 20601.9  1244.4
 21809.4 1236.13 25687.1  1234.7 27566.7 1239.43 28549.2 1295.18 29215.8 1335.84
#Mann= 20 ,-1 , 0
-28264.1     .05       0-27639.9     .12       0-21589.2     .12       0
-14824.6     .12       0-11384.7     .07       0-10522.6     .12       0
   -7936     .12       0 -5945.7     .12       0 -3588.7     .12       0
   735.2     .12       0    3024    .035       0  8007.7     .08       0
 10433.6     .12       0 16723.7     .08       0 18732.2     .05       0
 20601.9     .05       0 21809.4     .12       0 25687.1     .12       0
 27566.7     .12       0 28549.2     .12       0
Bank Sta=3024,8007.7
XS Rating Curve= 0 ,0
Exp/Cntr=0.3,0.1

Type RM Length L Ch R = 1 ,1561417 ,566,566,566
BEGIN DESCRIPTION:
Canyon Lake Dam UpStrm
END DESCRIPTION:
XS GIS Cut Line= 6
      2220455.71     13867545.11      2221846.04     13866383.04
      2222759.08     13862129.12      2222843.38     13861282.59
      2222426.71     13858400.65      2221470.81      13857289.1
#Sta/Elev= 30
  1036.8 1024.45  1090.9 1025.27  1505.1 1029.12  2008.3 1002.35  2128.6   999.1
  2342.9 1000.22    2606 1014.58  2832.9 1016.31    2870  1000.3  2899.7  966.65
  2958.6  915.85  2979.8  914.47  5430.6     900  7162.9  908.92    7511  982.27
  7836.9 1004.77  8239.9  994.88  8270.2  951.51  8290.4  942.98  9523.1  942.17
    9545  958.81  9914.3  973.88 10313.3  948.03 10865.6 1061.49 11042.1 1081.74
 11395.8 1110.89 11776.7  1114.7 12060.8 1119.72 12402.9 1126.08 12428.3  1125.4
#Mann= 15 ,-1 , 0
  1036.8     .05       0  1090.9     .12       0  2008.3     .05       0
  2128.6     .07       0  2342.9     .05       0    2606     .07       0
  2899.7     .12       0  2979.8    .035       0  9523.1     .07       0
  9914.3     .12       0 11042.1     .05       0 11395.8     .08       0
 11776.7     .05       0 12060.8     .08       0 12402.9     .05       0
#XS Ineff= 2 , 0
       0 7876.92 1004.51               0
Permanent Ineff=
       F       F
Bank Sta=2979.8,9523.1
XS Rating Curve= 0 ,0
Exp/Cntr=0.3,0.1

Type RM Length L Ch R = 1 ,1560851 ,932,932,932
BEGIN DESCRIPTION:
Canyon Lake Dam
END DESCRIPTION:
XS GIS Cut Line= 5
      2220580.23     13867586.59      2222323.31     13866424.54
      2223402.35     13862253.63      2222945.83     13860884.07
      2222510.35     13858188.21
#Sta/Elev= 30
   899.8  1024.6  1026.9 1023.59  1395.1 1012.39  1878.5  988.46  1957.2  974.06
  2014.3  986.29    2215  993.51    2483 1003.32  2845.3  997.67  2879.6  997.19
  2894.7  984.11  3025.9  991.68  3061.4  982.47  3076.9  965.58  5335.5  974.77
  7345.5  970.08  7624.8  992.87  8218.6  998.98  8578.8  981.22    8598   969.7
  8605.1  948.55  8610.4   943.1  8619.1     943    9852     943    9870   955.1
 10659.7  961.62   10811  985.47 11102.1 1060.05 11290.3 1083.89 11477.4 1107.29
#Mann= 10 ,-1 , 0
   899.8     .05       0  1026.9     .12       0  1395.1     .08       0
  1878.5     .12       0    2215     .05       0  2845.3     .12       0
  3076.9    .035       0    9870     .05       0   10811     .12       0
 11290.3     .05       0
Bank Sta=3076.9,9870
XS Rating Curve= 0 ,0
Exp/Cntr=0.3,0.1

Chan Stop Cuts=-1
Use User Specified Reach Order=0
Composite Channel Slope=5