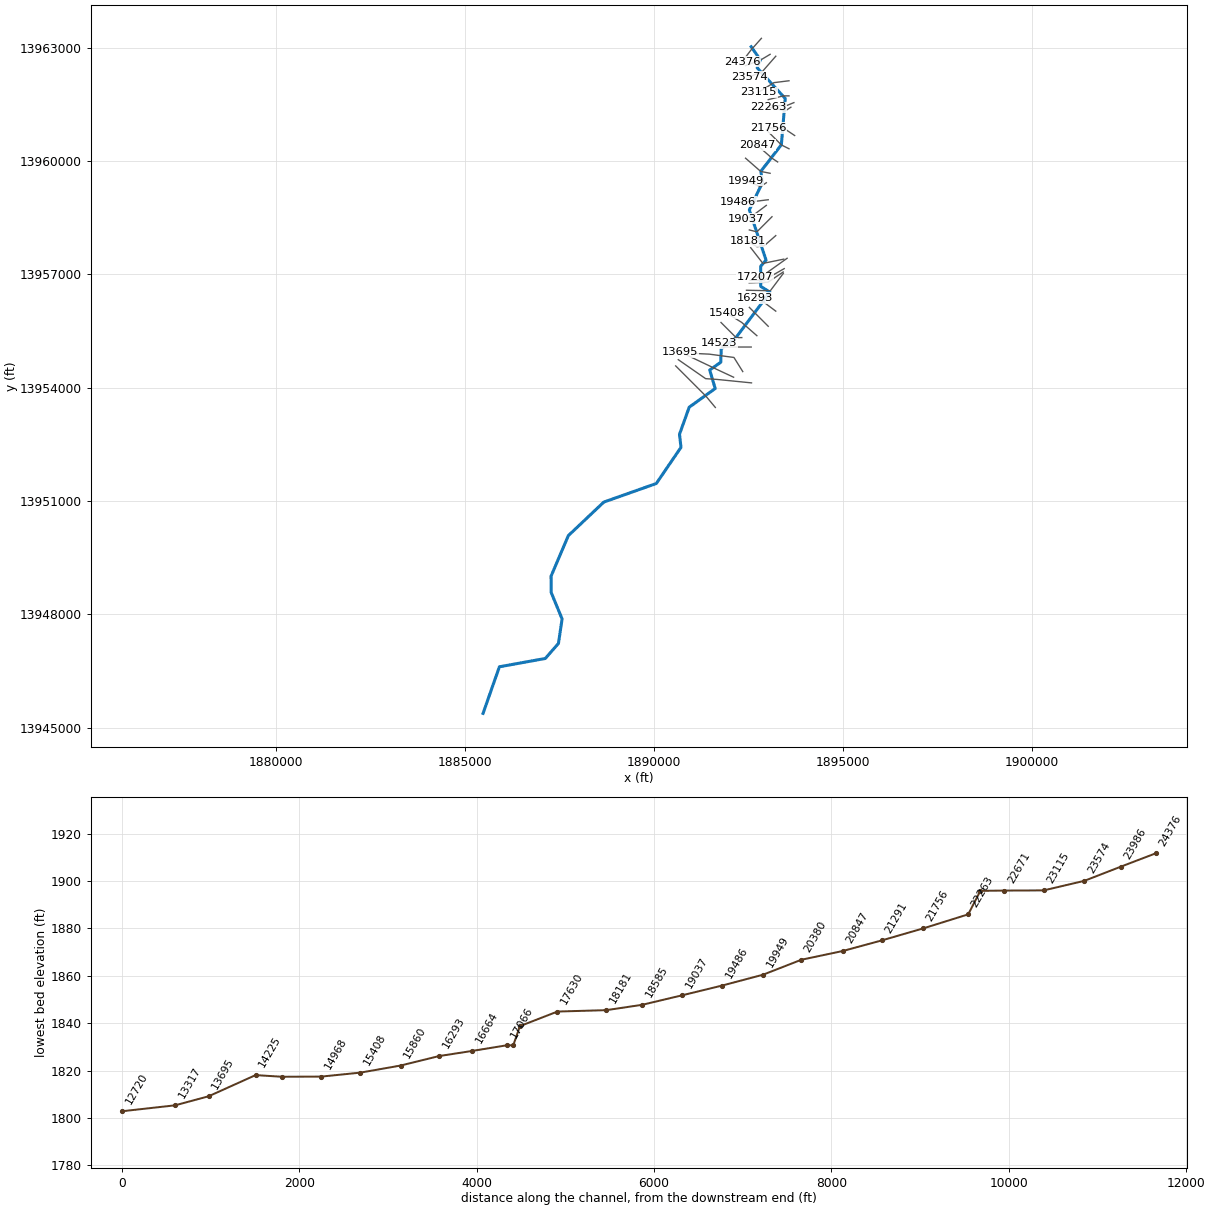
--- Henderson Branch.prj (project) ---

Proj Title=Henderson Branch Base Level Engineering
Current Plan=p01
Default Exp/Contr=0.3,0.1
English Units
Geom File=g01
Flow File=f01
Plan File=p01
BEGIN DESCRIPTION:
Henderson Branch
END DESCRIPTION:

--- Henderson Branch.p01 (plan) ---

Plan Title=Multiple Run
Short Identifier=Multiple
Geom File=g01
Flow File=f01
Subcritical Flow
K Sum by GR= 0
Std Step Tol= 0.01
Critical Tol= 0.01
Num of Std Step Trials= 20
Max Error Tol= 0.3
Flow Tol Ratio= 0.001
Split Flow NTrial= 30
Split Flow Tol= 0.02
Split Flow Ratio= 0.02
Log Output Level= 0
Friction Slope Method= 1
Unsteady Friction Slope Method= 2
Unsteady Bridges Friction Slope Method= 1
Parabolic Critical Depth
Global Vel Dist=  1 , 1 , 1
Global Log Level= 0
CheckData=True
Encroach Param= -1, 0, 0, 0
BEGIN DESCRIPTION:
Multiple Run
END DESCRIPTION:

--- Henderson Branch.f01 (steady flow) ---

Flow Title=Multiple
Number of Profiles=7
Profile Names=10-year,25-year,50-year,1pct_min,100-year,1pct_plu,500-year
River Rch & RM= Henderson Branch,Reach-1,24376
    2557    4574    6581    4564    9106   18169   17242
River Rch & RM= Henderson Branch,Reach-1,17207
    3239    5853    8475    5910   11793   23529   22586
River Rch & RM= Henderson Branch,Reach-1,13695
    3607    6542    9499    6638   13245   26427   25481
River Rch & RM= Henderson Branch,Reach-1,11788
    3834    6971   10136    7092   14151   28235   27293
River Rch & RM= Henderson Branch,Reach-1,9934
    4011    7296   10613    7427   14818   29565   28584
River Rch & RM= Henderson Branch,Reach-1,7877
    4320    7877   11477    8042   16047   32018   31042
River Rch & RM= Henderson Branch,Reach-1,5072
    5491   10103   14809   10432   20814   41530   40690
Boundary for River Rch & Prof#=Henderson Branch,Reach-1,1
Up Type=0
Dn Type=3
Dn Slope=0.005
Boundary for River Rch & Prof#=Henderson Branch,Reach-1,2
Up Type=0
Dn Type=3
Dn Slope=0.005
Boundary for River Rch & Prof#=Henderson Branch,Reach-1,3
Up Type=0
Dn Type=3
Dn Slope=0.005
Boundary for River Rch & Prof#=Henderson Branch,Reach-1,4
Up Type=0
Dn Type=3
Dn Slope=0.005
Boundary for River Rch & Prof#=Henderson Branch,Reach-1,5
Up Type=0
Dn Type=3
Dn Slope=0.005
Boundary for River Rch & Prof#=Henderson Branch,Reach-1,6
Up Type=0
Dn Type=3
Dn Slope=0.005
Boundary for River Rch & Prof#=Henderson Branch,Reach-1,7
Up Type=0
Dn Type=3
Dn Slope=0.005

--- Henderson Branch.g01 (geometry) ---

Geom Title=Existing Conditions

River Reach=Henderson Branch,Reach-1
Reach XY= 30
      1892575.00     13963025.00      1892816.98     13962678.31
      1892732.36     13962468.66      1893475.04     13961655.02
      1893372.93     13960430.86      1892830.45     13959727.45
      1892872.86     13959430.97      1892524.89     13958704.91
      1892967.93     13957375.00      1892825.60     13957214.38
      1892826.97     13956680.65      1893071.92     13956526.67
      1892161.53     13955311.43      1891780.80     13955027.30
      1891769.17     13954672.67      1891476.07     13954464.46
      1891621.56     13953976.43      1890932.93     13953481.39
      1890676.05     13952764.56      1890715.42     13952418.44
      1890061.74     13951461.34      1888672.50     13950969.65
      1887733.04     13950081.33      1887275.10     13949006.81
      1887276.82     13948581.12      1887567.44     13947875.00
      1887471.17     13947226.58      1887123.53     13946828.55
      1885908.21     13946608.56      1885475.00     13945375.00

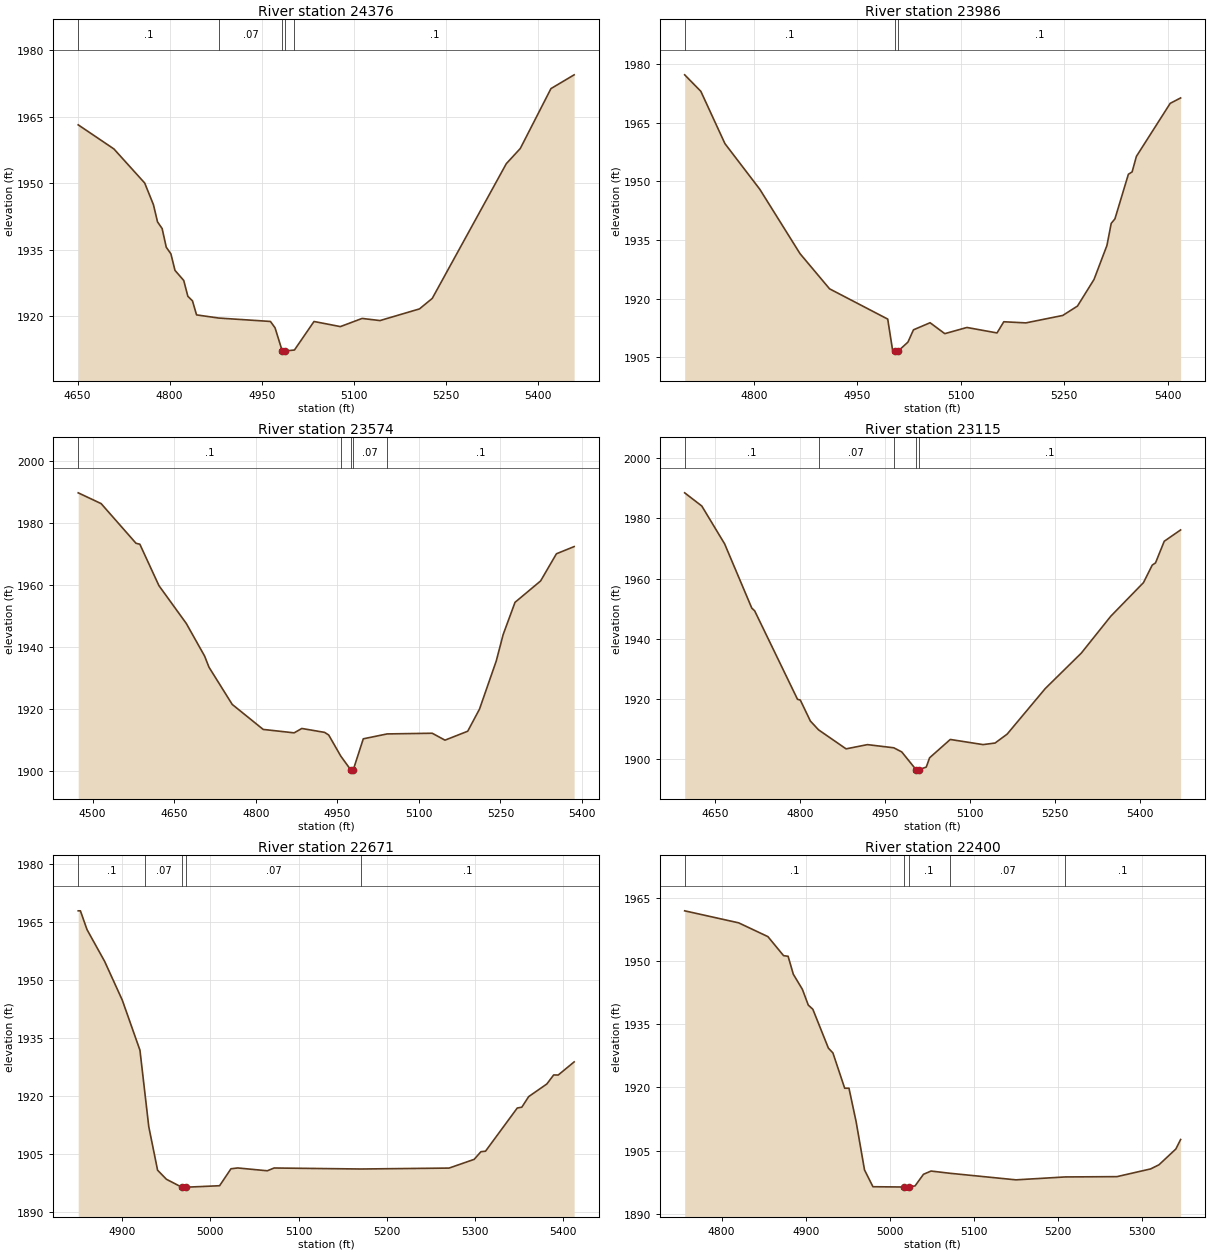
Type RM Length L Ch R = 1,24376,390,390,390
BEGIN DESCRIPTION:
Henderson Branch 52.0
END DESCRIPTION:
XS GIS Cut Line= 3
      1892844.40     13963248.37      1892568.50     13962938.33
      1892330.78     13962625.03
#Sta/Elev= 30
  4651.0 1963.17  4709.2 1957.73  4759.4 1950.03  4773.6 1945.15  4780.3 1941.26
  4787.8 1939.76  4794.5 1935.55  4802.1 1934.04  4808.7 1930.33  4823.0 1928.04
  4829.7 1924.47  4837.2 1923.45  4843.9 1920.27  4879.8 1919.56  4964.3 1918.79
  4971.8 1917.36  4983.5 1912.14  4983.9 1911.64  4988.5 1912.14  5003.4 1912.34
  5035.3 1918.78  5078.3 1917.63  5113.7 1919.47  5142.8 1918.99  5207.2 1921.62
  5228.0 1923.99  5348.7 1954.40  5371.5 1957.83  5421.5 1971.35  5459.3 1974.46
#Mann=5,-1,0
  4651.0     0.1       0  4879.8    0.07       0  4983.5    0.05       0
  4988.5    0.07       0  5003.4     0.1       0
Bank Sta=4983.5,4988.5
Exp/Cntr=0.3,0.1

Type RM Length L Ch R = 1,23986,412,412,412
BEGIN DESCRIPTION:
Henderson Branch 51.0
END DESCRIPTION:
XS GIS Cut Line= 3
      1893075.04     13962825.02      1892825.00     13962675.00
      1892424.99     13962525.00
#Sta/Elev= 30
  4699.9 1977.22  4723.3 1973.01  4758.3 1959.62  4808.8 1947.96  4867.1 1931.50
  4909.9 1922.51  4994.2 1914.77  5001.3 1906.76  5004.1 1906.57  5004.5 1906.07
  5009.2 1906.57  5023.5 1908.89  5031.5 1912.03  5055.6 1913.84  5076.9 1911.05
  5109.0 1912.63  5152.6 1911.23  5162.4 1914.09  5194.4 1913.80  5247.8 1915.70
  5269.2 1918.10  5293.2 1924.91  5311.9 1933.59  5318.1 1939.24  5323.5 1940.40
  5343.0 1951.80  5348.4 1952.40  5354.6 1956.37  5403.6 1969.93  5418.7 1971.31
#Mann=3,-1,0
  4699.9     0.1       0  5004.1    0.05       0  5009.2     0.1       0
Bank Sta=5004.1,5009.2
Exp/Cntr=0.3,0.1

Type RM Length L Ch R = 1,23574,459,459,459
BEGIN DESCRIPTION:
Henderson Branch 50.0
END DESCRIPTION:
XS GIS Cut Line= 3
      1893225.00     13962775.00      1892875.00     13962375.00
      1892524.99     13962225.00
#Sta/Elev= 30
  4473.4 1989.85  4515.6 1986.37  4579.7 1973.58  4586.8 1973.27  4621.9 1959.91
  4672.2 1947.72  4705.9 1937.20  4714.0 1933.59  4756.7 1921.60  4813.7 1913.53
  4870.6 1912.43  4884.8 1913.84  4926.6 1912.58  4934.2 1911.73  4956.5 1904.90
  4974.4 1900.58  4974.8 1900.08  4979.5 1900.58  4997.8 1910.50  5041.7 1912.08
  5124.6 1912.30  5148.1 1910.07  5189.9 1912.95  5211.6 1920.09  5242.4 1935.61
  5255.1 1944.13  5276.9 1954.52  5324.0 1961.43  5353.1 1970.19  5385.7 1972.51
#Mann=5,-1,0
  4473.4     0.1       0  4956.5    0.07       0  4974.4    0.05       0
  4979.5    0.07       0  5041.7     0.1       0
Bank Sta=4974.4,4979.5
Exp/Cntr=0.3,0.1

Type RM Length L Ch R = 1,23115,444,444,444
BEGIN DESCRIPTION:
Henderson Branch 49.0
END DESCRIPTION:
XS GIS Cut Line= 3
      1893574.96     13962124.99      1893175.00     13962075.00
      1892774.97     13961824.98
#Sta/Elev= 30
  4596.7 1988.48  4626.9 1984.10  4667.2 1971.52  4715.1 1950.18  4720.1 1949.31
  4795.7 1919.91  4800.7 1919.63  4818.4 1912.69  4832.8 1909.76  4881.4 1903.44
  4919.1 1904.84  4965.6 1903.79  4979.6 1902.42  5004.8 1896.54  5005.2 1896.04
  5010.0 1896.54  5022.8 1897.38  5028.7 1900.47  5065.2 1906.56  5123.0 1904.85
  5144.2 1905.37  5165.5 1908.33  5232.7 1923.46  5296.4 1935.26  5348.2 1947.47
  5406.0 1958.66  5421.4 1964.46  5427.2 1965.20  5442.6 1972.39  5471.5 1976.16
#Mann=5,-1,0
  4596.7     0.1       0  4832.8    0.07       0  4965.6     0.1       0
  5004.8    0.05       0  5010.0     0.1       0
Bank Sta=5004.8,5010
Exp/Cntr=0.3,0.1

Type RM Length L Ch R = 1,22671,271,271,271
BEGIN DESCRIPTION:
Henderson Branch 48.0
END DESCRIPTION:
XS GIS Cut Line= 3
      1893574.96     13961725.00      1893425.00     13961725.00
      1893024.97     13961624.99
#Sta/Elev= 30
  4850.1 1967.88  4852.6 1967.88  4860.1 1963.02  4880.1 1954.80  4900.1 1944.79
  4920.1 1931.86  4925.7 1920.81  4930.1 1912.12  4940.1 1900.85  4950.1 1898.51
  4967.5 1896.46  4967.9 1895.96  4972.7 1896.46  5010.4 1896.84  5023.3 1901.22
  5031.0 1901.43  5064.5 1900.70  5072.2 1901.42  5170.7 1901.16  5270.6 1901.40
  5299.0 1903.65  5306.7 1905.63  5311.9 1905.76  5347.9 1916.92  5353.1 1917.14
  5360.8 1919.86  5381.4 1923.13  5389.2 1925.47  5394.3 1925.44  5412.4 1928.84
#Mann=5,-1,0
  4850.1     0.1       0  4925.7    0.07       0  4967.5    0.05       0
  4972.7    0.07       0  5170.7     0.1       0
Bank Sta=4967.5,4972.7
Exp/Cntr=0.3,0.1

Type RM Length L Ch R = 1,22400,137,137,137
BEGIN DESCRIPTION:
Henderson Branch 47.1
END DESCRIPTION:
XS GIS Cut Line= 4
      1893704.53     13961546.40      1893526.96     13961473.50
      1893417.59     13961469.86      1893129.26     13961462.58
#Sta/Elev= 30
  4756.1 1961.86  4820.3 1959.01  4855.1 1955.74  4873.7 1951.23  4879.1 1951.08
  4885.3 1946.82  4896.1 1943.24  4903.1 1939.50  4908.5 1938.52  4927.0 1929.30
  4932.4 1928.15  4946.4 1919.78  4951.5 1919.78  4960.0 1911.84  4970.0 1900.39
  4980.0 1896.42  5017.5 1896.35  5017.9 1895.85  5022.7 1896.35  5030.1 1896.62
  5040.1 1899.37  5049.1 1900.14  5071.1 1899.62  5150.1 1898.05  5208.6 1898.74
  5270.1 1898.81  5310.2 1900.64  5320.2 1901.63  5340.2 1905.36  5345.9 1907.62
#Mann=5,-1,0
  4756.1     0.1       0  5017.5    0.05       0  5022.7     0.1       0
  5071.1    0.07       0  5208.6     0.1       0
Bank Sta=5017.5,5022.7
Exp/Cntr=0.3,0.1

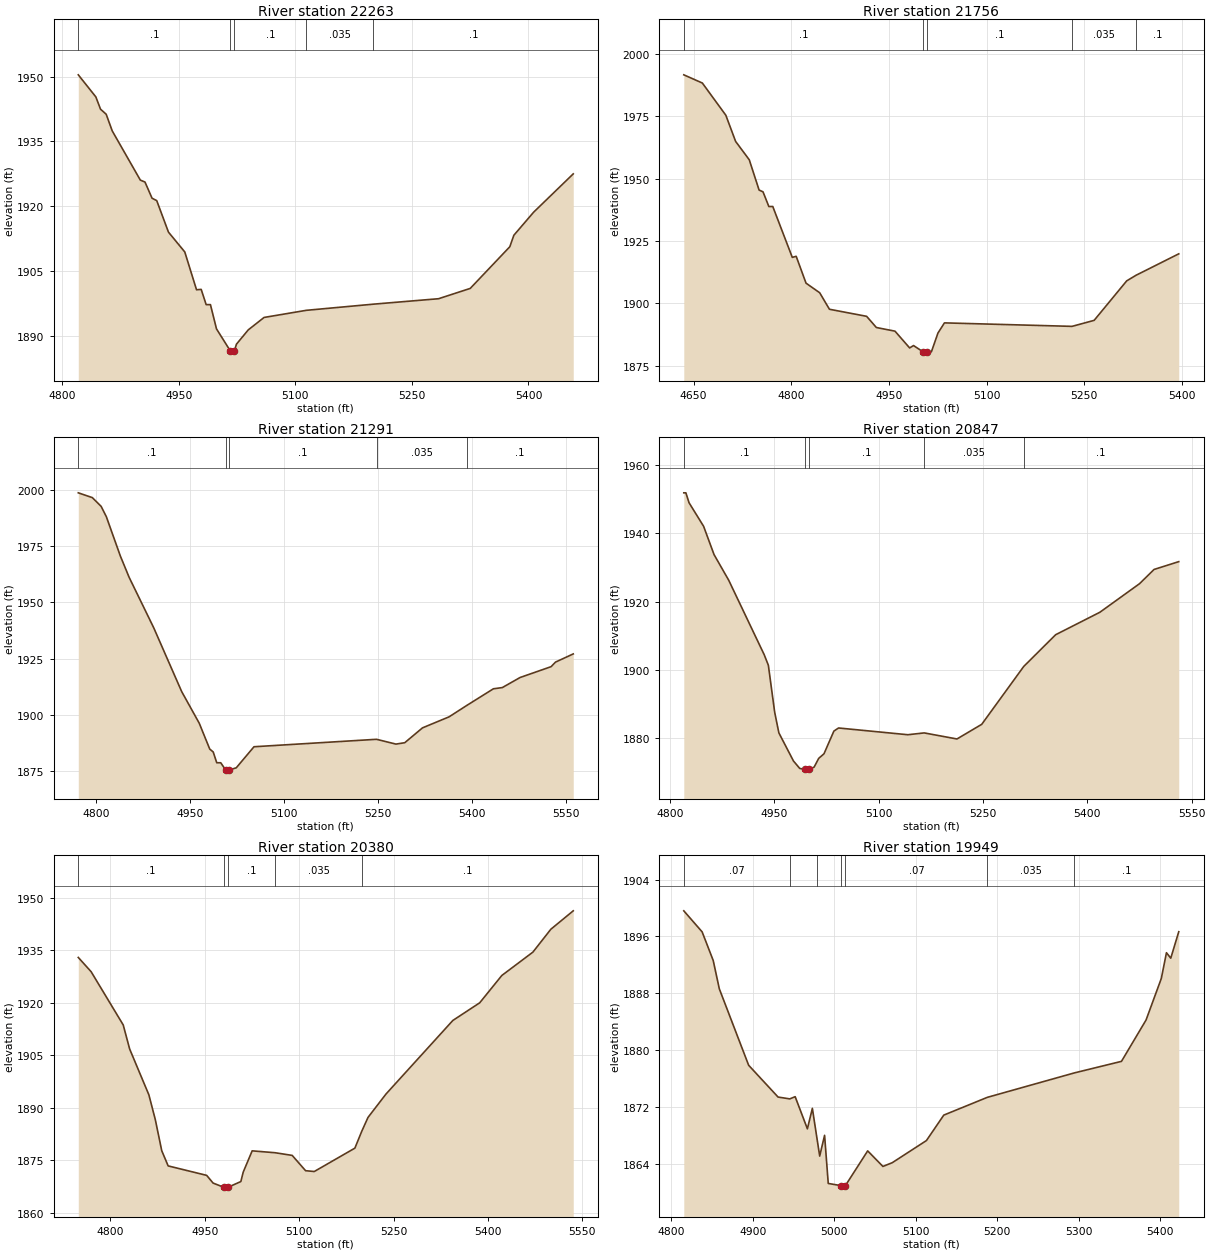
Type RM Length L Ch R = 1,22263,507,507,507
BEGIN DESCRIPTION:
Henderson Branch 47.0
END DESCRIPTION:
XS GIS Cut Line= 3
      1893625.00     13961425.00      1893485.24     13961332.92
      1893025.03     13961424.99
#Sta/Elev= 30
  4820.9 1950.44  4843.5 1945.32  4849.5 1942.48  4856.8 1941.30  4864.6 1937.43
  4900.7 1926.04  4906.7 1925.59  4915.8 1921.84  4921.8 1921.28  4936.9 1913.98
  4957.9 1909.38  4973.0 1900.62  4979.0 1900.70  4985.4 1897.17  4990.9 1897.17
  4998.7 1891.55  5016.5 1886.43  5016.9 1885.93  5021.7 1886.43  5024.3 1887.99
  5039.5 1891.31  5059.9 1894.20  5114.1 1895.85  5200.6 1897.28  5284.3 1898.54
  5325.1 1900.93  5376.0 1910.59  5381.2 1913.25  5406.6 1918.59  5457.6 1927.48
#Mann=5,-1,0
  4820.9     0.1       0  5016.5    0.05       0  5021.7     0.1       0
  5114.1   0.035       0  5200.6     0.1       0
Bank Sta=5016.5,5021.7
Exp/Cntr=0.3,0.1

Type RM Length L Ch R = 1,21756,465,465,465
BEGIN DESCRIPTION:
Henderson Branch 46.0
END DESCRIPTION:
XS GIS Cut Line= 3
      1893724.98     13960675.01      1893425.00     13960875.00
      1893025.03     13960875.00
#Sta/Elev= 30
  4634.9 1991.61  4663.4 1988.32  4699.5 1975.40  4714.5 1964.92  4735.5 1957.54
  4750.6 1945.40  4756.6 1944.70  4765.6 1938.79  4771.6 1938.82  4801.6 1918.41
  4807.6 1918.83  4822.7 1908.07  4843.7 1904.22  4858.7 1897.60  4915.8 1894.77
  4930.8 1890.28  4959.4 1888.82  4981.9 1882.09  4987.9 1883.05  5002.6 1880.51
  5003.1 1880.01  5008.2 1880.51  5015.4 1880.57  5025.4 1888.06  5035.4 1892.14
  5231.4 1890.74  5265.4 1893.15  5315.4 1908.98  5330.0 1911.27  5395.4 1919.82
#Mann=5,-1,0
  4634.9     0.1       0  5002.6    0.05       0  5008.2     0.1       0
  5231.4   0.035       0  5330.0     0.1       0
Bank Sta=5002.6,5008.2
Exp/Cntr=0.3,0.1

Type RM Length L Ch R = 1,21291,444,444,444
BEGIN DESCRIPTION:
Henderson Branch 45.0
END DESCRIPTION:
XS GIS Cut Line= 3
      1893575.02     13960324.99      1893375.00     13960425.00
      1892975.01     13960824.99
#Sta/Elev= 30
  4772.1 1998.61  4794.5 1996.48  4808.5 1992.61  4816.8 1988.03  4839.2 1970.53
  4853.2 1961.06  4892.3 1938.71  4937.0 1910.30  4965.0 1896.25  4981.7 1884.79
  4987.3 1883.46  4992.9 1878.69  4999.3 1878.69  5007.1 1875.47  5007.5 1874.97
  5012.7 1875.47  5024.0 1876.44  5052.3 1885.80  5247.7 1889.11  5278.6 1886.98
  5292.7 1887.59  5321.0 1894.19  5363.4 1899.09  5391.8 1904.18  5434.1 1911.55
  5448.3 1912.09  5476.6 1916.56  5526.1 1921.38  5533.1 1923.40  5561.4 1927.04
#Mann=5,-1,0
  4772.1     0.1       0  5007.1    0.05       0  5012.7     0.1       0
  5247.7   0.035       0  5391.8     0.1       0
Bank Sta=5007.1,5012.7
Exp/Cntr=0.3,0.1

Type RM Length L Ch R = 1,20847,467,467,467
BEGIN DESCRIPTION:
Henderson Branch 44.0
END DESCRIPTION:
XS GIS Cut Line= 3
      1893274.97     13959975.02      1893125.00     13960075.00
      1892725.03     13960424.97
#Sta/Elev= 30
  4819.8 1951.74  4822.8 1951.74  4827.3 1948.86  4848.3 1941.96  4863.3 1933.70
  4884.4 1926.21  4935.4 1904.47  4941.4 1901.37  4950.5 1887.64  4956.5 1881.64
  4977.5 1873.42  4986.5 1871.25  4994.2 1870.96  4994.7 1870.46  4999.9 1870.96
  5007.2 1871.64  5013.8 1874.19  5021.4 1875.53  5035.6 1882.15  5042.3 1883.06
  5141.9 1881.09  5165.5 1881.62  5212.6 1879.85  5248.2 1884.13  5308.6 1901.03
  5354.5 1910.30  5418.1 1916.86  5475.1 1925.20  5496.0 1929.36  5531.5 1931.64
#Mann=5,-1,0
  4819.8     0.1       0  4994.2    0.05       0  4999.9     0.1       0
  5165.5   0.035       0  5308.6     0.1       0
Bank Sta=4994.2,4999.9
Exp/Cntr=0.3,0.1

Type RM Length L Ch R = 1,20380,431,431,431
BEGIN DESCRIPTION:
Henderson Branch 43.0
END DESCRIPTION:
XS GIS Cut Line= 3
      1893074.99     13959675.00      1892825.00     13959725.00
      1892424.96     13960075.03
#Sta/Elev= 30
  4749.0 1932.92  4769.4 1928.85  4820.4 1913.65  4830.6 1906.79  4861.2 1893.68
  4871.4 1886.61  4881.6 1877.75  4891.8 1873.40  4953.0 1870.70  4963.2 1868.50
  4980.6 1867.27  4981.1 1866.77  4986.5 1867.27  5007.3 1868.93  5011.1 1871.63
  5025.3 1877.70  5061.8 1877.16  5088.9 1876.40  5110.2 1872.03  5124.0 1871.80
  5188.5 1878.47  5199.5 1883.31  5209.4 1887.25  5237.9 1893.91  5344.2 1914.93
  5386.9 1919.97  5422.0 1927.77  5471.4 1934.44  5499.9 1940.97  5535.5 1946.23
#Mann=5,-1,0
  4749.0     0.1       0  4980.6    0.05       0  4986.5     0.1       0
  5061.8   0.035       0  5199.5     0.1       0
Bank Sta=4980.6,4986.5
Exp/Cntr=0.3,0.1

Type RM Length L Ch R = 1,19949,463,463,463
BEGIN DESCRIPTION:
Henderson Branch 42.0
END DESCRIPTION:
XS GIS Cut Line= 3
      1892975.01     13959425.01      1892825.00     13959325.00
      1892424.99     13959475.00
#Sta/Elev= 30
  4815.2 1899.61  4837.7 1896.65  4851.3 1892.63  4858.8 1888.64  4894.8 1877.89
  4930.9 1873.42  4945.3 1873.16  4951.9 1873.47  4966.9 1868.95  4973.0 1871.83
  4978.6 1867.65  4982.0 1865.12  4988.0 1868.04  4992.5 1861.27  5007.7 1860.97
  5008.2 1860.47  5013.6 1860.97  5040.9 1865.85  5059.6 1863.66  5071.1 1864.19
  5113.0 1867.30  5134.3 1870.88  5187.8 1873.38  5294.4 1876.81  5352.4 1878.44
  5382.6 1884.26  5401.3 1890.10  5407.6 1893.72  5412.9 1892.95  5422.7 1896.67
#Mann=7,-1,0
  4815.2    0.07       0  4945.3     0.1       0  4978.6    0.07       0
  5007.7    0.05       0  5013.6    0.07       0  5187.8   0.035       0
  5294.4     0.1       0
Bank Sta=5007.7,5013.6
Exp/Cntr=0.3,0.1

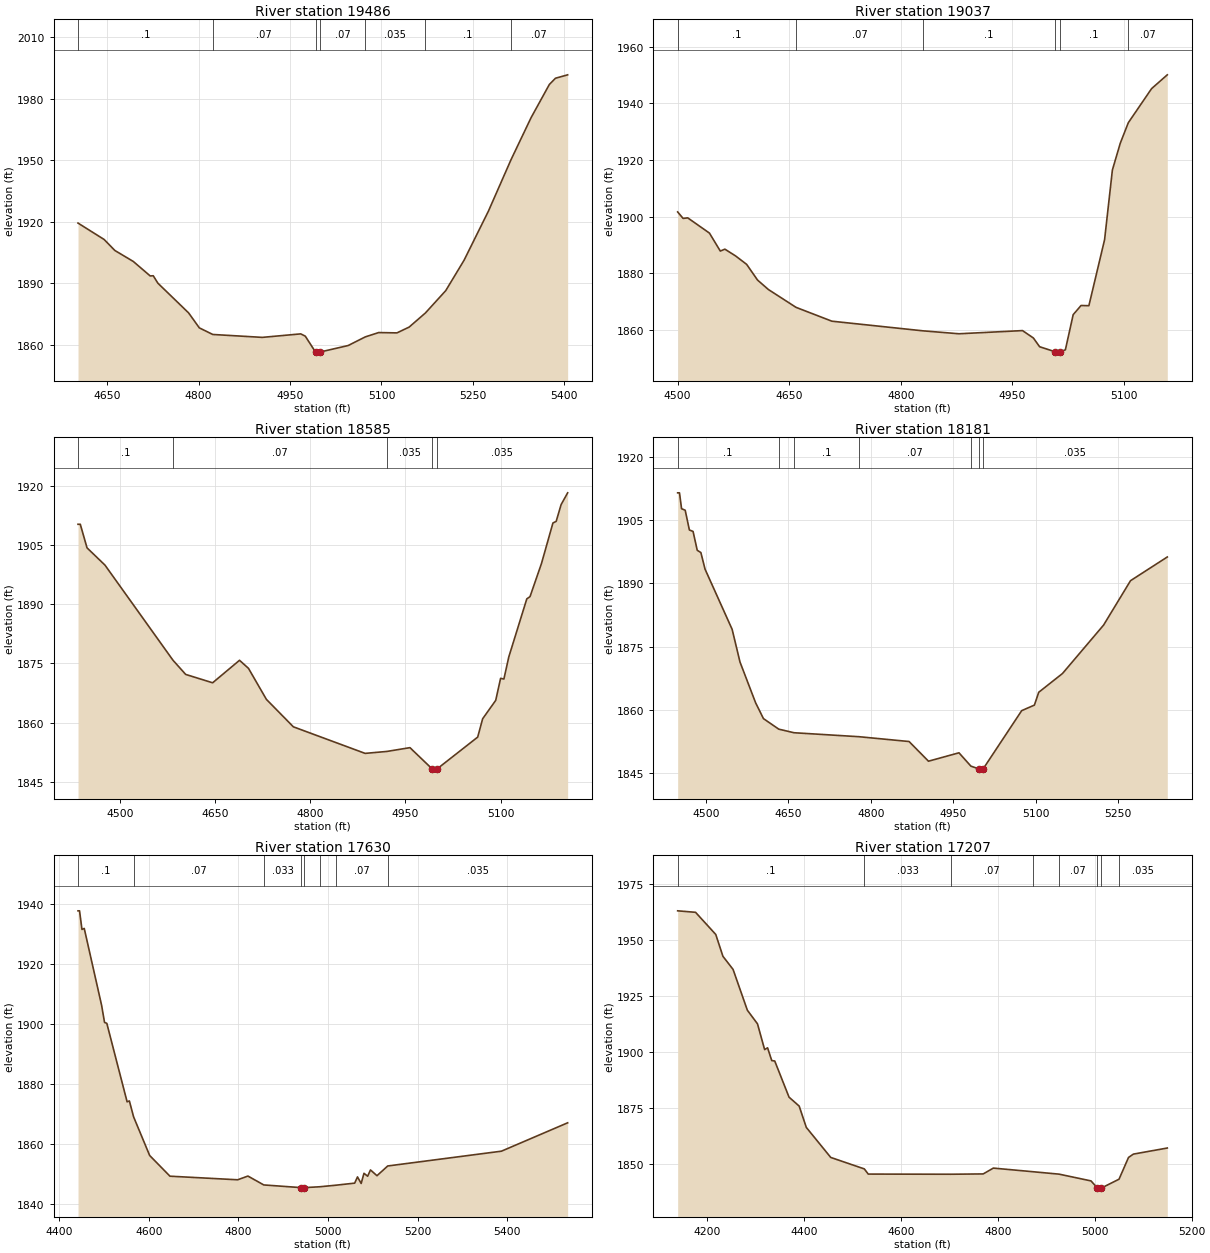
Type RM Length L Ch R = 1,19486,449,449,449
BEGIN DESCRIPTION:
Henderson Branch 41.0
END DESCRIPTION:
XS GIS Cut Line= 3
      1893024.96     13958975.00      1892625.00     13958925.00
      1892224.97     13958925.00
#Sta/Elev= 30
  4602.3 1919.38  4645.1 1911.38  4662.7 1906.01  4693.0 1900.63  4720.7 1893.57
  4725.7 1893.66  4733.3 1890.03  4783.7 1875.52  4801.3 1868.21  4823.3 1864.99
  4904.6 1863.57  4967.6 1865.28  4975.1 1864.15  4991.9 1856.38  4992.4 1855.88
  4998.7 1856.38  5045.4 1859.59  5073.5 1863.81  5095.4 1865.92  5125.4 1865.76
  5145.4 1868.59  5172.1 1875.49  5205.4 1886.38  5235.4 1901.18  5275.4 1925.18
  5312.4 1950.25  5345.4 1970.84  5375.4 1987.06  5385.4 1990.10  5405.4 1991.77
#Mann=7,-1,0
  4602.3     0.1       0  4823.3    0.07       0  4991.9    0.05       0
  4998.7    0.07       0  5073.5   0.035       0  5172.1     0.1       0
  5312.4    0.07       0
Bank Sta=4991.9,4998.7
Exp/Cntr=0.3,0.1

Type RM Length L Ch R = 1,19037,452,452,452
BEGIN DESCRIPTION:
Henderson Branch 40.0
END DESCRIPTION:
XS GIS Cut Line= 3
      1892975.00     13958825.00      1892575.00     13958525.00
      1892425.01     13958475.00
#Sta/Elev= 30
  4500.0 1901.67  4507.3 1899.38  4513.5 1899.58  4542.7 1894.20  4557.3 1887.85
  4563.5 1888.52  4578.1 1886.08  4592.7 1883.15  4607.3 1877.62  4621.9 1874.27
  4659.1 1867.96  4707.3 1863.07  4829.5 1859.67  4878.1 1858.63  4963.5 1859.75
  4978.1 1857.14  4986.5 1854.05  5007.1 1852.29  5007.6 1851.79  5013.9 1852.29
  5021.1 1852.95  5031.6 1865.38  5042.2 1868.62  5052.7 1868.54  5073.8 1891.85
  5084.3 1916.49  5094.9 1925.95  5105.7 1933.19  5137.0 1945.24  5158.1 1950.11
#Mann=6,-1,0
  4500.0     0.1       0  4659.1    0.07       0  4829.5     0.1       0
  5007.1    0.05       0  5013.9     0.1       0  5105.7    0.07       0
Bank Sta=5007.1,5013.9
Exp/Cntr=0.3,0.1

Type RM Length L Ch R = 1,18585,404,404,404
BEGIN DESCRIPTION:
Henderson Branch 39.0
END DESCRIPTION:
XS GIS Cut Line= 3
      1893125.03     13958525.03      1892725.00     13958125.00
      1892524.98     13958175.00
#Sta/Elev= 30
  4433.9 1910.22  4437.5 1910.22  4448.1 1904.26  4476.4 1899.89  4583.6 1875.83
  4603.6 1872.24  4646.1 1870.12  4688.5 1875.81  4702.6 1873.78  4730.9 1865.92
  4773.4 1858.98  4886.5 1852.26  4920.8 1852.75  4957.2 1853.71  4992.6 1848.27
  4993.1 1847.77  4999.5 1848.27  5064.0 1856.38  5071.8 1861.02  5092.4 1865.67
  5100.1 1871.25  5105.3 1871.07  5113.0 1876.65  5141.4 1891.35  5146.5 1891.93
  5164.5 1900.28  5182.6 1910.55  5187.7 1910.96  5195.5 1915.20  5205.8 1918.18
#Mann=5,-1,0
  4433.9     0.1       0  4583.6    0.07       0  4920.8   0.035       0
  4992.6   0.035       0  4999.5   0.035       0
Bank Sta=4992.6,4999.5
Exp/Cntr=0.3,0.1

Type RM Length L Ch R = 1,18181,551,551,551
BEGIN DESCRIPTION:
Henderson Branch 38.0
END DESCRIPTION:
XS GIS Cut Line= 4
      1893224.97     13958024.97      1892918.07     13957756.44
      1892727.18     13957730.90      1892475.03     13957874.98
#Sta/Elev= 30
  4448.8 1911.41  4452.1 1911.41  4455.9 1907.65  4462.5 1907.29  4470.1 1902.62
  4476.8 1902.27  4484.4 1897.81  4491.0 1897.27  4498.6 1893.34  4547.9 1879.09
  4562.2 1871.35  4590.7 1861.67  4604.9 1857.95  4632.7 1855.46  4660.4 1854.61
  4778.6 1853.67  4869.8 1852.53  4905.1 1847.87  4960.6 1849.86  4982.3 1846.70
  4997.4 1846.02  4997.9 1845.52  5004.4 1846.02  5074.7 1859.84  5097.8 1861.15
  5105.7 1864.19  5148.9 1868.63  5223.7 1880.10  5272.7 1890.61  5339.6 1896.22
#Mann=7,-1,0
  4448.8     0.1       0  4632.7    0.07       0  4660.4     0.1       0
  4778.6    0.07       0  4982.3   0.035       0  4997.4   0.035       0
  5004.4   0.035       0
Bank Sta=4997.4,5004.4
Exp/Cntr=0.3,0.1

Type RM Length L Ch R = 1,17630,423,423,423
BEGIN DESCRIPTION:
Henderson Branch 37.0
END DESCRIPTION:
XS GIS Cut Line= 3
      1893436.63     13957402.17      1892884.42     13957288.86
      1892559.68     13957707.33
#Sta/Elev= 30
  4441.8 1937.86  4445.2 1937.86  4450.6 1931.65  4455.7 1931.98  4494.5 1906.30
  4501.0 1900.60  4506.1 1900.30  4551.4 1874.09  4556.5 1874.37  4565.9 1869.07
  4601.8 1856.16  4647.1 1849.25  4798.3 1848.05  4821.2 1849.29  4856.6 1846.33
  4940.2 1845.43  4940.7 1844.93  4947.2 1845.43  4981.7 1845.72  5017.6 1846.24
  5059.6 1846.93  5065.9 1849.01  5074.1 1846.82  5080.4 1850.22  5088.6 1849.23
  5094.9 1851.34  5109.4 1849.41  5133.4 1852.66  5387.3 1857.60  5535.2 1867.07
#Mann=8,-1,0
  4441.8     0.1       0  4565.9    0.07       0  4856.6   0.033       0
  4940.2   0.035       0  4947.2   0.033       0  4981.7   0.035       0
  5017.6    0.07       0  5133.4   0.035       0
Bank Sta=4940.2,4947.2
Exp/Cntr=0.3,0.1

Type RM Length L Ch R = 1,17207,76,76,76
BEGIN DESCRIPTION:
Henderson Branch 36.0
END DESCRIPTION:
XS GIS Cut Line= 3
      1893524.99     13957424.99      1892825.00     13956925.00
      1892675.02     13956925.00
#Sta/Elev= 30
  4139.4 1963.10  4176.3 1962.44  4218.0 1952.54  4232.8 1942.78  4253.7 1936.93
  4283.2 1918.70  4304.1 1912.62  4318.8 1901.12  4324.9 1901.91  4333.5 1896.22
  4339.7 1896.01  4369.2 1879.86  4390.1 1875.88  4404.8 1866.36  4455.2 1852.95
  4524.5 1847.82  4532.6 1845.51  4702.5 1845.44  4769.8 1845.58  4790.7 1848.18
  4871.5 1846.58  4926.4 1845.48  4992.2 1842.46  5005.4 1839.29  5005.9 1838.79
  5013.8 1839.29  5050.0 1843.22  5069.6 1852.94  5079.6 1854.43  5149.6 1857.15
#Mann=8,-1,0
  4139.4     0.1       0  4524.5   0.033       0  4702.5    0.07       0
  4871.5   0.035       0  4926.4    0.07       0  5005.4    0.05       0
  5013.8    0.07       0  5050.0   0.035       0
Bank Sta=5005.4,5013.8
Exp/Cntr=0.3,0.1

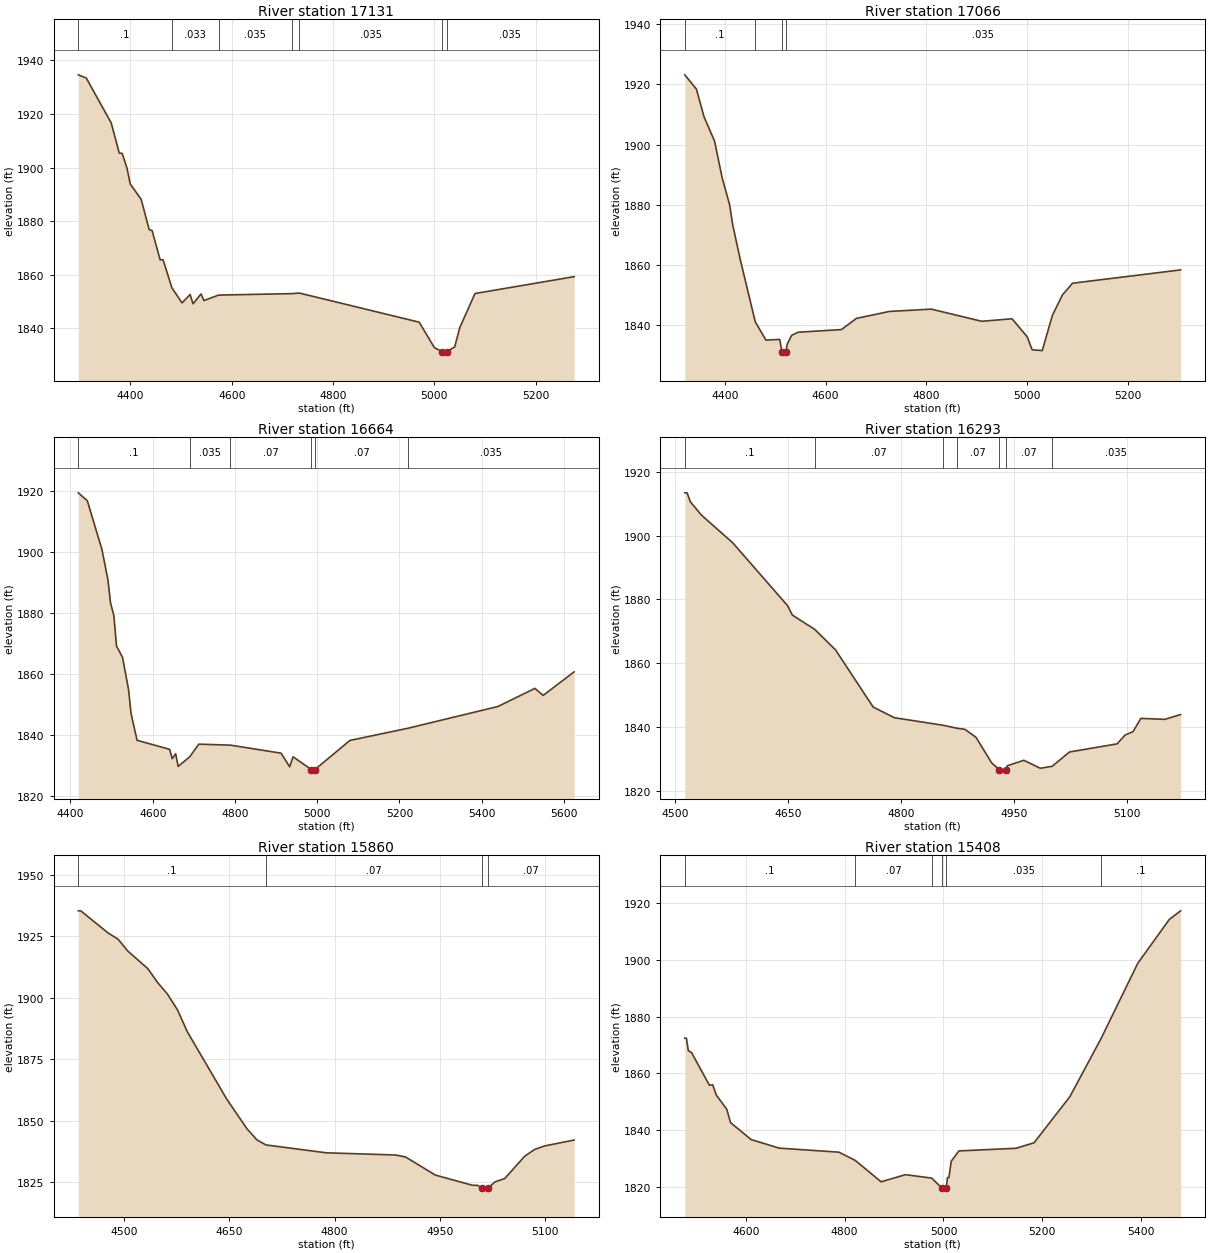
Type RM Length L Ch R = 1,17131,65,65,65
BEGIN DESCRIPTION:
Mapping XS 6db17c56
END DESCRIPTION:
XS GIS Cut Line= 3
      1893448.66     13957150.78      1892921.28     13956851.20
      1892549.25     13956840.69
#Sta/Elev= 30
  4297.1 1934.62  4312.8 1933.41  4362.0 1916.66  4377.9 1905.39  4383.6 1905.29
  4393.3 1899.66  4399.5 1893.86  4421.1 1888.13  4437.0 1876.78  4442.7 1876.45
  4458.6 1865.51  4464.4 1865.52  4481.7 1855.10  4501.8 1849.42  4517.7 1852.56
  4523.5 1849.10  4539.3 1852.77  4545.1 1850.29  4573.8 1852.34  4719.0 1852.89
  4733.4 1853.10  4969.9 1842.22  4999.9 1832.72  5015.8 1831.16  5016.3 1830.66
  5024.2 1831.16  5040.0 1832.97  5050.0 1840.18  5080.0 1852.92  5275.8 1859.23
#Mann=7,-1,0
  4297.1     0.1       0  4481.7   0.033       0  4573.8   0.035       0
  4719.0    0.07       0  4733.4   0.035       0  5015.8   0.035       0
  5024.2   0.035       0
Bank Sta=5015.8,5024.2
Exp/Cntr=0.3,0.1

Type RM Length L Ch R = 1,17066,402,402,402
BEGIN DESCRIPTION:
Mapping XS 06bee267
END DESCRIPTION:
XS GIS Cut Line= 3
      1893420.91     13957061.76      1893021.29     13956791.01
      1892520.71     13956773.33
#Sta/Elev= 30
  4320.8 1923.15  4343.9 1918.40  4358.9 1909.23  4379.9 1901.11  4394.8 1889.06
  4409.8 1879.93  4415.8 1873.40  4430.8 1861.85  4460.5 1841.18  4481.7 1835.08
  4509.1 1835.30  4513.4 1831.25  4513.9 1830.75  4521.8 1831.25  4523.6 1833.61
  4532.6 1836.62  4545.4 1837.69  4631.5 1838.57  4661.4 1842.29  4726.6 1844.59
  4809.8 1845.36  4909.9 1841.32  4969.9 1842.16  4999.9 1836.21  5009.9 1831.85
  5029.9 1831.60  5049.9 1843.23  5070.0 1850.10  5090.0 1853.96  5304.4 1858.38
#Mann=4,-1,0
  4320.8     0.1       0  4460.5   0.035       0  4513.4   0.035       0
  4521.8   0.035       0
Bank Sta=4513.4,4521.8
Exp/Cntr=0.3,0.1

Type RM Length L Ch R = 1,16664,371,371,371
BEGIN DESCRIPTION:
Henderson Branch 35.0
END DESCRIPTION:
XS GIS Cut Line= 3
      1893425.03     13957025.04      1893081.36     13956565.70
      1892449.66     13956578.14
#Sta/Elev= 30
  4419.2 1919.24  4441.1 1916.63  4476.6 1900.73  4491.2 1890.80  4497.4 1883.32
  4505.7 1879.04  4512.0 1869.17  4526.6 1865.49  4541.2 1855.04  4547.4 1847.11
  4562.0 1838.37  4641.2 1835.41  4647.4 1832.36  4655.8 1833.98  4662.0 1829.82
  4690.1 1832.99  4712.1 1837.11  4789.1 1836.78  4912.1 1834.16  4933.0 1829.72
  4941.3 1832.97  4985.9 1828.79  4986.4 1828.29  4994.4 1828.79  5079.3 1838.31
  5221.1 1842.32  5439.3 1849.41  5529.3 1855.33  5549.3 1853.03  5624.7 1860.74
#Mann=6,-1,0
  4419.2     0.1       0  4690.1   0.035       0  4789.1    0.07       0
  4985.9    0.05       0  4994.4    0.07       0  5221.1   0.035       0
Bank Sta=4985.9,4994.4
Exp/Cntr=0.3,0.1

Type RM Length L Ch R = 1,16293,433,433,433
BEGIN DESCRIPTION:
Henderson Branch 34.0
END DESCRIPTION:
XS GIS Cut Line= 3
      1893225.00     13956025.00      1892825.00     13956325.00
      1892675.01     13956375.00
#Sta/Elev= 30
  4512.8 1913.44  4515.9 1913.44  4520.1 1910.65  4534.7 1906.50  4576.3 1897.79
  4649.3 1878.03  4655.5 1875.11  4685.3 1870.59  4712.8 1864.20  4762.8 1846.25
  4790.9 1842.90  4855.6 1840.53  4874.1 1839.59  4884.7 1839.24  4899.3 1836.75
  4920.1 1828.73  4930.0 1826.64  4930.5 1826.14  4939.4 1826.64  4940.9 1827.83
  4962.8 1829.54  4984.7 1827.05  5000.4 1827.65  5023.3 1832.14  5086.6 1834.69
  5097.1 1837.44  5107.7 1838.53  5118.2 1842.69  5149.8 1842.38  5170.9 1843.89
#Mann=7,-1,0
  4512.8     0.1       0  4685.3    0.07       0  4855.6     0.1       0
  4874.1    0.07       0  4930.0    0.05       0  4939.4    0.07       0
  5000.4   0.035       0
Bank Sta=4930,4939.4
Exp/Cntr=0.3,0.1

Type RM Length L Ch R = 1,15860,452,452,452
BEGIN DESCRIPTION:
Henderson Branch 33.0
END DESCRIPTION:
XS GIS Cut Line= 3
      1893025.00     13955625.00      1892625.00     13956025.00
      1892525.00     13956125.00
#Sta/Elev= 30
  4434.5 1935.40  4438.0 1935.40  4476.9 1926.40  4491.1 1923.89  4505.2 1918.99
  4533.5 1911.91  4547.6 1906.22  4561.8 1901.44  4575.9 1895.10  4590.1 1886.10
  4646.6 1858.58  4674.9 1846.75  4689.1 1842.21  4702.0 1840.14  4788.0 1836.93
  4887.0 1836.04  4901.2 1835.23  4943.6 1827.87  4996.6 1823.71  5003.7 1823.71
  5009.6 1822.65  5010.1 1822.15  5018.6 1822.15  5019.1 1822.65  5028.5 1825.07
  5042.6 1826.46  5070.9 1835.49  5085.0 1838.25  5099.2 1839.71  5141.6 1842.13
#Mann=4,-1,0
  4434.5     0.1       0  4702.0    0.07       0  5009.6    0.05       0
  5019.1    0.07       0
Bank Sta=5009.6,5019.1
Exp/Cntr=0.3,0.1

Type RM Length L Ch R = 1,15408,440,440,440
BEGIN DESCRIPTION:
Henderson Branch 32.0
END DESCRIPTION:
XS GIS Cut Line= 3
      1892724.96     13955375.03      1892325.00     13955725.00
      1891924.96     13955975.02
#Sta/Elev= 30
  4476.6 1872.38  4479.9 1872.38  4483.7 1867.99  4490.3 1867.30  4526.4 1855.81
  4533.0 1855.98  4540.6 1852.25  4561.5 1847.36  4569.1 1842.64  4610.9 1836.64
  4667.8 1833.62  4788.3 1832.20  4821.3 1829.32  4873.8 1821.76  4923.1 1824.26
  4976.2 1823.06  4996.1 1819.67  4996.6 1819.17  5005.7 1819.67  5008.1 1823.25
  5011.0 1823.25  5015.7 1828.98  5031.1 1832.64  5146.6 1833.57  5183.2 1835.50
  5255.7 1851.77  5318.9 1872.28  5393.1 1898.79  5456.8 1914.24  5479.8 1917.29
#Mann=6,-1,0
  4476.6     0.1       0  4821.3    0.07       0  4976.2   0.035       0
  4996.1   0.035       0  5005.7   0.035       0  5318.9     0.1       0
Bank Sta=4996.1,5005.7
Exp/Cntr=0.3,0.1

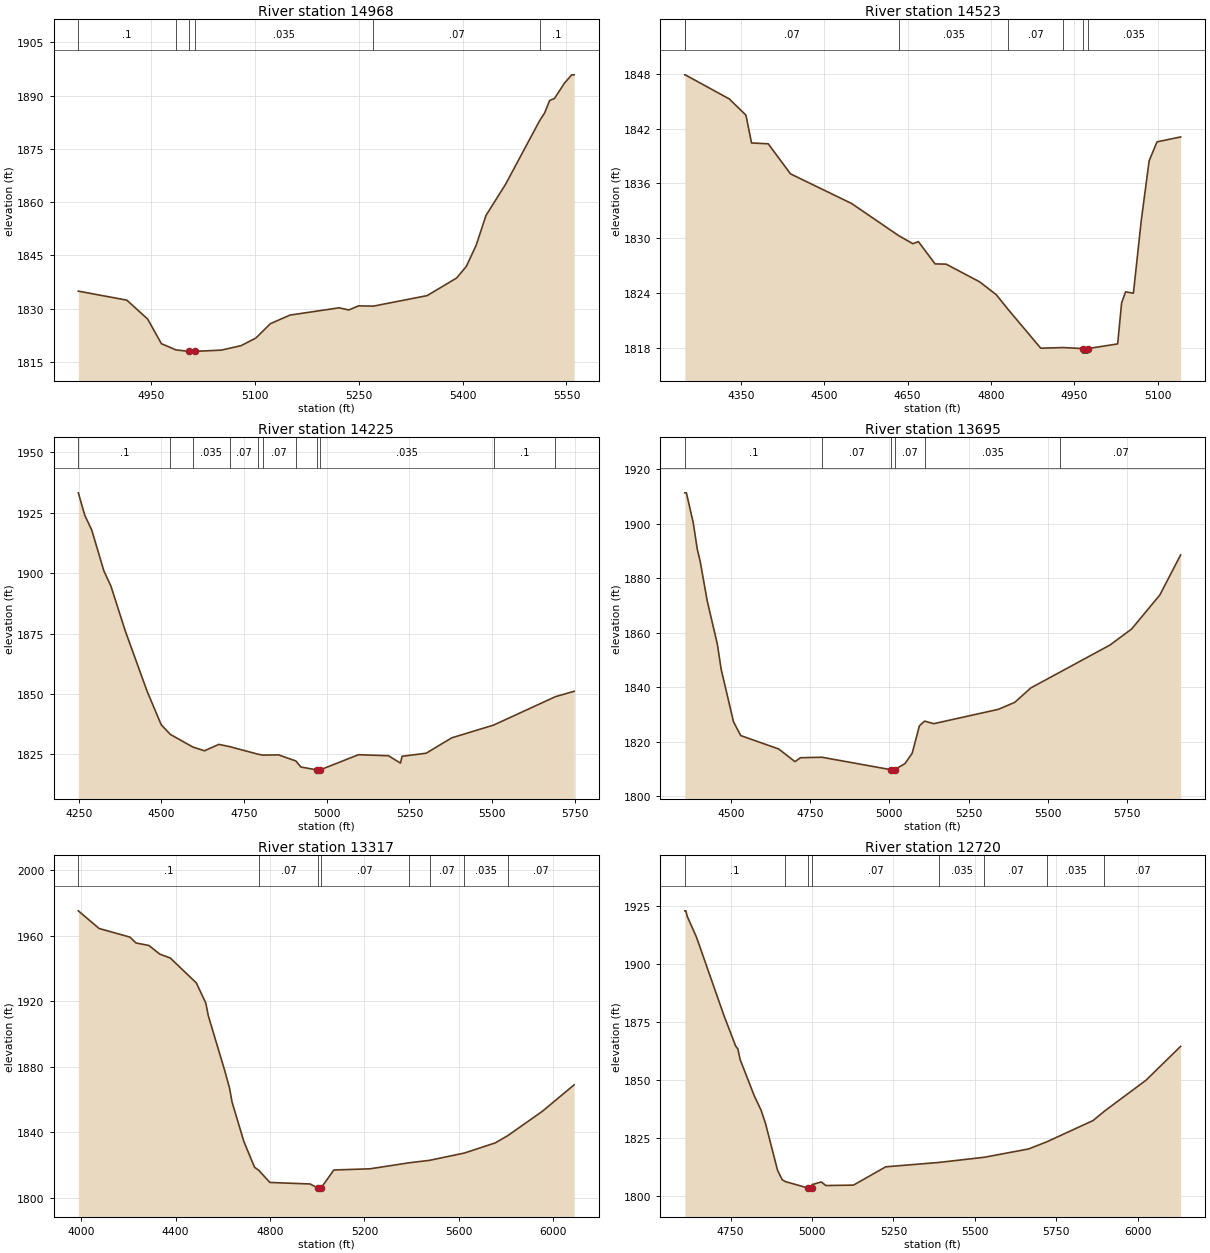
Type RM Length L Ch R = 1,14968,445,445,445
BEGIN DESCRIPTION:
Henderson Branch 31.0
END DESCRIPTION:
XS GIS Cut Line= 3
      1892324.99     13955325.00      1892175.00     13955325.00
      1891774.98     13955725.02
#Sta/Elev= 30
  4845.4 1834.96  4915.4 1832.42  4945.4 1827.11  4965.4 1820.14  4986.5 1818.40
  5004.7 1818.00  5005.2 1817.50  5014.3 1818.00  5052.0 1818.35  5080.2 1819.60
  5101.5 1821.72  5122.7 1825.80  5150.9 1828.21  5221.7 1830.26  5235.8 1829.66
  5249.9 1830.81  5271.4 1830.74  5348.9 1833.70  5391.4 1838.65  5405.5 1841.94
  5419.7 1847.91  5433.8 1856.26  5462.1 1865.05  5511.1 1882.91  5518.6 1885.19
  5525.7 1888.66  5532.8 1889.24  5546.9 1893.48  5557.5 1895.88  5561.1 1895.88
#Mann=6,-1,0
  4845.4     0.1       0  4986.5   0.035       0  5004.7   0.035       0
  5014.3   0.035       0  5271.4    0.07       0  5511.1     0.1       0
Bank Sta=5004.7,5014.3
Exp/Cntr=0.3,0.1

Type RM Length L Ch R = 1,14523,298,298,298
BEGIN DESCRIPTION:
Henderson Branch 30.0
END DESCRIPTION:
XS GIS Cut Line= 3
      1892575.04     13955075.00      1891825.00     13955075.00
      1891724.97     13955175.03
#Sta/Elev= 30
  4249.5 1847.89  4250.3 1847.89  4329.5 1845.25  4359.5 1843.47  4369.5 1840.43
  4399.5 1840.34  4439.5 1837.05  4549.5 1833.80  4633.9 1830.29  4659.5 1829.40
  4669.5 1829.63  4699.5 1827.19  4719.5 1827.16  4779.5 1825.23  4809.5 1823.82
  4831.2 1822.18  4889.5 1817.96  4929.8 1818.03  4964.7 1817.92  4965.2 1817.42
  4973.9 1817.42  4974.4 1817.92  5027.8 1818.43  5034.9 1822.92  5042.0 1824.13
  5056.1 1823.98  5070.2 1831.92  5084.4 1838.47  5098.5 1840.55  5141.0 1841.09
#Mann=7,-1,0
  4249.5     0.1       0  4250.3    0.07       0  4633.9   0.035       0
  4831.2    0.07       0  4929.8   0.035       0  4964.7   0.035       0
  4974.4   0.035       0
Bank Sta=4964.7,4974.4
Exp/Cntr=0.3,0.1

Type RM Length L Ch R = 1,14225,530,530,530
BEGIN DESCRIPTION:
Henderson Branch 29.0
END DESCRIPTION:
XS GIS Cut Line= 4
      1892351.17     13954424.83      1892117.39     13954798.62
      1891466.69     13954886.41      1891065.54     13954906.09
#Sta/Elev= 30
  4249.1 1933.14  4268.6 1923.87  4289.8 1917.70  4326.4 1900.85  4347.6 1894.61
  4390.8 1876.15  4457.2 1851.09  4499.7 1837.28  4527.3 1833.30  4595.6 1828.06
  4630.6 1826.53  4673.9 1829.18  4706.8 1828.24  4792.9 1825.10  4806.7 1824.74
  4854.4 1824.83  4906.6 1822.34  4922.0 1819.83  4970.1 1818.62  4970.6 1818.12
  4979.8 1818.62  5096.0 1824.90  5186.8 1824.48  5223.0 1821.45  5228.0 1824.25
  5300.7 1825.52  5378.3 1831.89  5504.5 1837.14  5691.7 1848.90  5748.2 1851.13
#Mann=11,-1,0
  4249.1     0.1       0  4527.3    0.07       0  4595.6   0.035       0
  4706.8    0.07       0  4792.9   0.035       0  4806.7    0.07       0
  4906.6   0.035       0  4970.1   0.035       0  4979.8   0.035       0
  5504.5     0.1       0  5691.7    0.07       0
Bank Sta=4970.1,4979.8
Exp/Cntr=0.3,0.1

Type RM Length L Ch R = 1,13695,378,378,378
BEGIN DESCRIPTION:
Mapping XS d8d976a5
END DESCRIPTION:
XS GIS Cut Line= 3
      1892109.03     13954274.95      1891673.65     13954478.25
      1890695.89     13954944.18
#Sta/Elev= 30
  4354.9 1911.28  4359.9 1911.28  4381.4 1900.37  4394.2 1890.66  4403.5 1886.09
  4425.6 1871.65  4457.3 1855.90  4469.7 1846.50  4508.5 1827.29  4531.3 1822.23
  4651.1 1817.31  4702.4 1812.67  4719.7 1814.11  4787.5 1814.28  5006.0 1809.69
  5006.5 1809.19  5016.3 1809.69  5049.3 1811.96  5072.0 1815.77  5094.7 1825.81
  5111.1 1827.53  5140.1 1826.60  5343.5 1831.85  5395.3 1834.41  5446.3 1839.73
  5539.6 1845.60  5696.0 1855.46  5764.1 1861.34  5853.0 1873.82  5918.5 1888.51
#Mann=6,-1,0
  4354.9     0.1       0  4787.5    0.07       0  5006.0    0.05       0
  5016.3    0.07       0  5111.1   0.035       0  5539.6    0.07       0
Bank Sta=5006,5016.3
Exp/Cntr=0.3,0.1

Type RM Length L Ch R = 1,13317,597,597,597
BEGIN DESCRIPTION:
Henderson Branch 28.1
END DESCRIPTION:
XS GIS Cut Line= 4
      1892582.50     13954125.55      1891659.55     13954218.04
      1891368.13     13954237.39      1890644.38     13954740.03
#Sta/Elev= 30
  3987.8 1975.25  4075.7 1964.48  4206.4 1959.21  4232.3 1955.64  4286.8 1954.10
  4332.7 1948.85  4377.2 1946.46  4487.8 1931.25  4528.0 1918.91  4538.5 1911.19
  4608.4 1877.57  4628.5 1867.05  4638.9 1858.64  4688.8 1834.63  4734.2 1818.76
  4752.8 1816.79  4799.3 1809.45  4970.0 1808.51  5004.9 1805.87  5005.4 1805.37
  5015.3 1805.87  5070.3 1817.04  5223.4 1817.78  5388.5 1821.43  5476.0 1822.94
  5623.8 1827.41  5754.2 1833.59  5806.9 1837.97  5954.2 1852.91  6088.6 1869.05
#Mann=8,-1,0
  3987.8     0.1       0  4752.8    0.07       0  5004.9    0.05       0
  5015.3    0.07       0  5388.5   0.035       0  5476.0    0.07       0
  5623.8   0.035       0  5806.9    0.07       0
Bank Sta=5004.9,5015.3
Exp/Cntr=0.3,0.1

Type RM Length L Ch R = 1,12720,460,460,460
BEGIN DESCRIPTION:
Henderson Branch 28.0
END DESCRIPTION:
XS GIS Cut Line= 3
      1891625.03     13953474.97      1891375.00     13953775.00
      1890575.02     13954574.98
#Sta/Elev= 30
  4609.7 1922.99  4613.0 1922.99  4616.9 1920.69  4645.5 1911.66  4730.1 1877.72
  4765.9 1864.60  4772.5 1863.41  4779.6 1858.78  4822.6 1843.29  4844.0 1836.87
  4857.7 1831.09  4894.2 1811.11  4908.5 1806.98  4918.4 1806.13  4987.5 1803.38
  4988.0 1802.88  4998.7 1803.38  5000.3 1804.82  5028.5 1805.98  5042.7 1804.43
  5127.5 1804.61  5226.5 1812.51  5390.7 1814.41  5528.8 1816.63  5664.9 1820.21
  5720.4 1823.27  5862.9 1832.48  5897.6 1836.52  6025.6 1849.91  6131.6 1864.50
#Mann=8,-1,0
  4609.7     0.1       0  4918.4    0.07       0  4987.5    0.05       0
  4998.7    0.07       0  5390.7   0.035       0  5528.8    0.07       0
  5720.4   0.035       0  5897.6    0.07       0
Bank Sta=4987.5,4998.7
Exp/Cntr=0.3,0.1