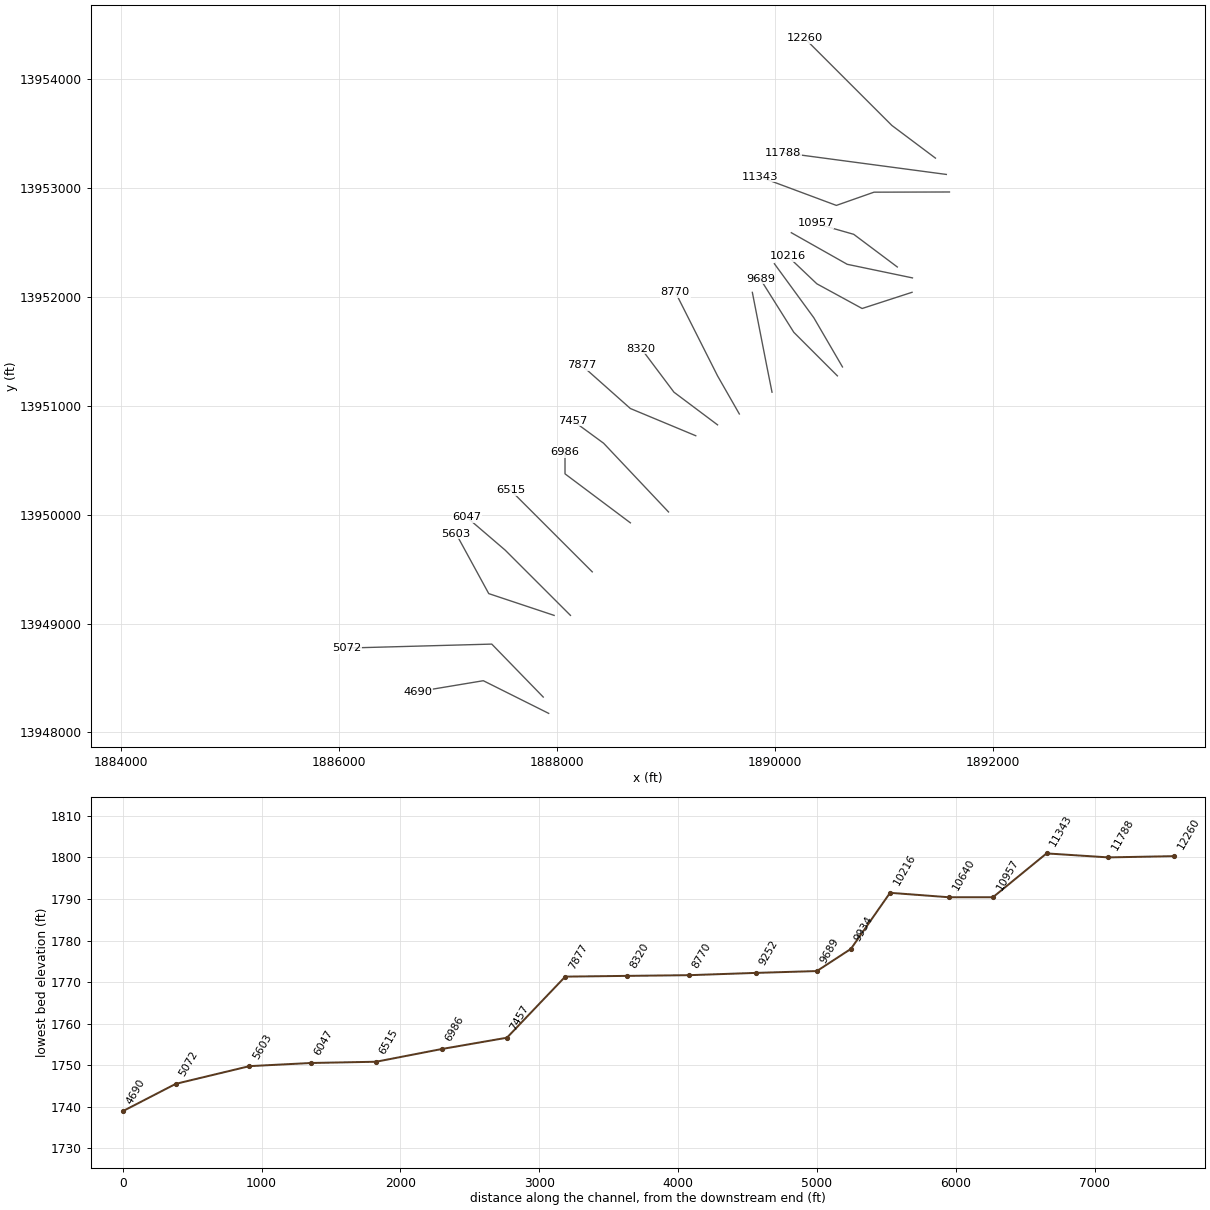
HEC-RAS study Henderson Branch.prj: Henderson Branch Base Level Engineering

--- Henderson Branch.g01 (geometry) --- (continued)

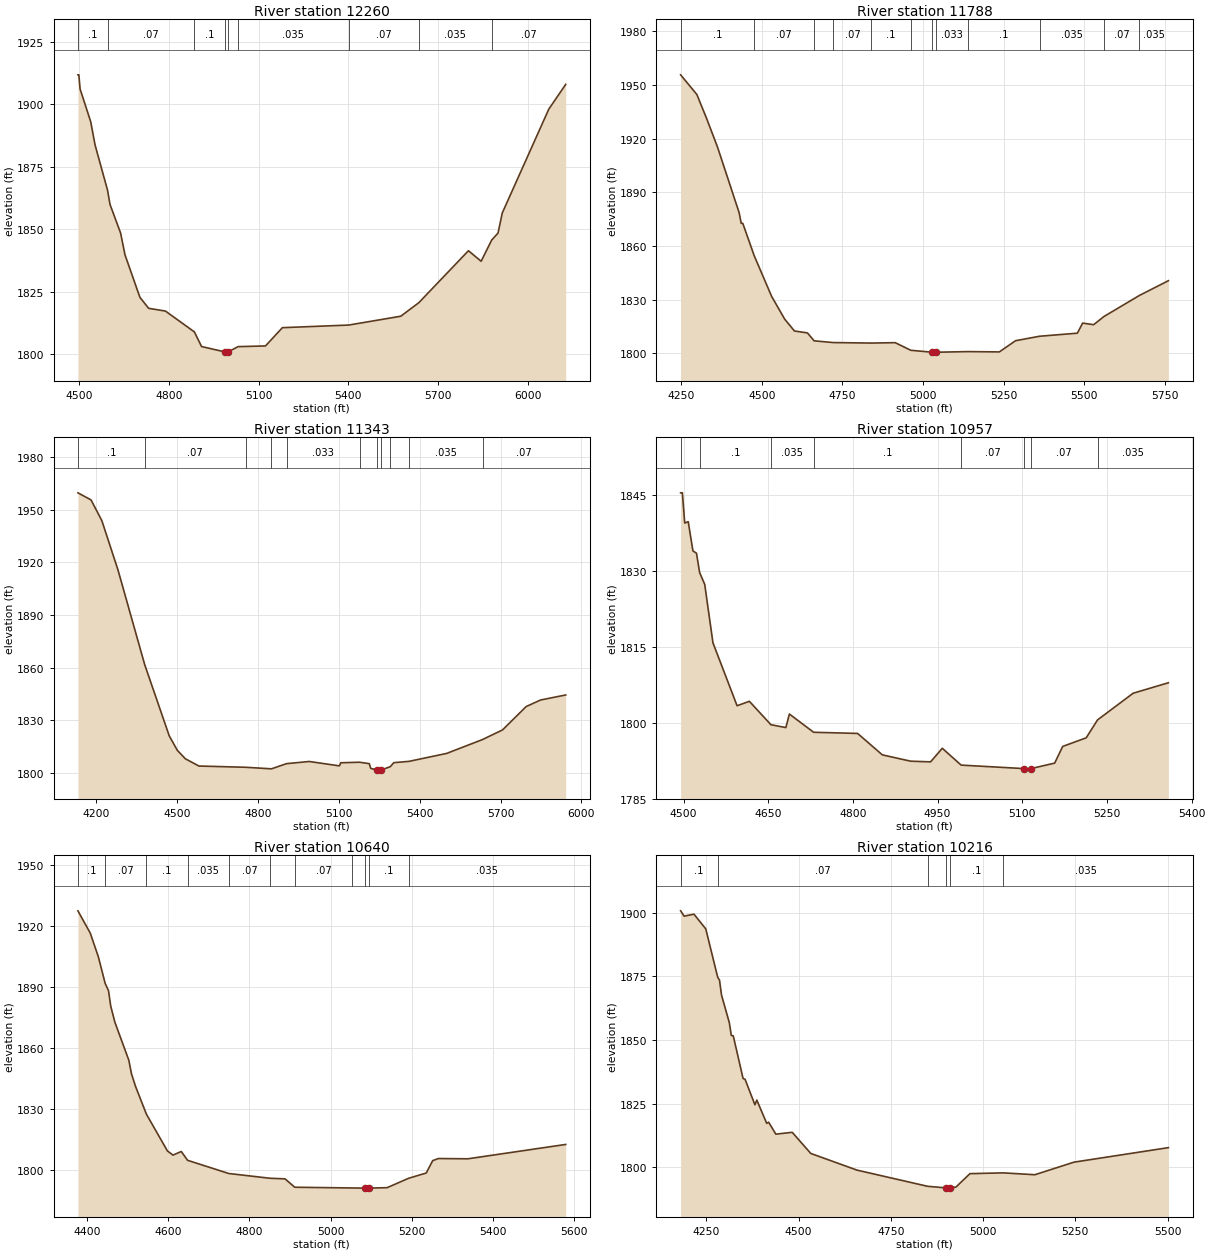
Type RM Length L Ch R = 1,12260,472,472,472
BEGIN DESCRIPTION:
Henderson Branch 27.0
END DESCRIPTION:
XS GIS Cut Line= 3
      1891474.99     13953275.01      1891075.00     13953575.00
      1890274.97     13954375.03
#Sta/Elev= 30
  4495.4 1911.85  4498.5 1911.85  4502.7 1906.15  4538.1 1893.08  4552.7 1883.77
  4594.4 1865.63  4602.7 1859.91  4638.1 1848.46  4652.7 1839.76  4702.7 1822.69
  4731.8 1818.28  4788.1 1817.18  4884.9 1808.82  4908.9 1802.96  4986.7 1800.82
  4987.2 1800.32  4997.9 1800.82  5031.0 1802.92  5122.7 1803.20  5179.2 1810.52
  5401.3 1811.57  5575.2 1815.11  5635.6 1820.54  5801.5 1841.36  5843.9 1837.13
  5879.2 1845.63  5900.5 1848.45  5914.6 1856.48  6070.2 1898.09  6126.8 1908.03
#Mann=9,-1,0
  4495.4     0.1       0  4594.4    0.07       0  4884.9     0.1       0
  4986.7    0.05       0  4997.9     0.1       0  5031.0   0.035       0
  5401.3    0.07       0  5635.6   0.035       0  5879.2    0.07       0
Bank Sta=4986.7,4997.9
Exp/Cntr=0.3,0.1

Type RM Length L Ch R = 1,11788,445,445,445
BEGIN DESCRIPTION:
Henderson Branch 26.0
END DESCRIPTION:
XS GIS Cut Line= 3
      1891574.96     13953125.01      1890825.00     13953225.00
      1890075.04     13953325.00
#Sta/Elev= 30
  4248.2 1955.75  4298.6 1944.74  4328.9 1931.31  4362.9 1915.20  4429.8 1878.58
  4436.1 1872.71  4441.1 1872.63  4476.4 1854.57  4530.6 1831.76  4571.0 1819.05
  4601.3 1812.41  4641.6 1811.33  4662.5 1806.90  4721.6 1805.93  4840.2 1805.65
  4914.0 1805.87  4962.2 1801.61  5029.2 1800.52  5029.7 1800.02  5041.0 1800.52
  5138.6 1800.87  5236.8 1800.70  5287.3 1806.97  5361.8 1809.47  5479.0 1811.18
  5495.4 1816.84  5529.4 1815.93  5561.6 1820.52  5671.4 1832.29  5761.4 1840.55
#Mann=12,-1,0
  4248.2     0.1       0  4476.4    0.07       0  4662.5     0.1       0
  4721.6    0.07       0  4840.2     0.1       0  4962.2   0.033       0
  5029.2   0.033       0  5041.0   0.033       0  5138.6     0.1       0
  5361.8   0.035       0  5561.6    0.07       0  5671.4   0.035       0
Bank Sta=5029.2,5041
Exp/Cntr=0.3,0.1

Type RM Length L Ch R = 1,11343,386,386,386
BEGIN DESCRIPTION:
Henderson Branch 25.0
END DESCRIPTION:
XS GIS Cut Line= 4
      1891603.72     13952963.81      1890911.06     13952962.08
      1890565.58     13952840.55      1889862.46     13953102.70
#Sta/Elev= 30
  4132.5 1959.72  4181.2 1955.67  4221.2 1943.86  4281.2 1915.69  4380.1 1861.77
  4471.2 1821.11  4501.2 1812.85  4531.2 1808.01  4581.2 1803.89  4754.1 1803.18
  4850.4 1802.29  4906.2 1805.24  4990.6 1806.48  5102.3 1803.98  5107.6 1805.75
  5177.3 1806.06  5213.2 1805.24  5218.6 1802.57  5243.0 1801.48  5243.5 1800.98
  5254.8 1801.48  5291.3 1803.54  5304.2 1805.80  5360.5 1806.55  5500.4 1811.09
  5633.2 1818.99  5707.4 1824.48  5795.0 1837.79  5848.3 1841.54  5941.8 1844.42
#Mann=11,-1,0
  4132.5     0.1       0  4380.1    0.07       0  4754.1     0.1       0
  4850.4    0.07       0  4906.2   0.033       0  5177.3     0.1       0
  5243.0   0.033       0  5254.8     0.1       0  5291.3    0.07       0
  5360.5   0.035       0  5633.2    0.07       0
Bank Sta=5243,5254.8
Exp/Cntr=0.3,0.1

Type RM Length L Ch R = 1,10957,317,317,317
BEGIN DESCRIPTION:
Henderson Branch 24.0
END DESCRIPTION:
XS GIS Cut Line= 3
      1891124.98     13952275.02      1890725.00     13952575.00
      1890374.98     13952675.01
#Sta/Elev= 30
  4494.8 1845.51  4497.9 1845.51  4502.1 1839.53  4508.3 1839.80  4516.6 1834.02
  4522.9 1833.56  4528.5 1829.73  4537.5 1827.39  4552.1 1815.82  4594.8 1803.37
  4616.6 1804.25  4654.8 1799.61  4681.2 1799.05  4687.5 1801.73  4730.4 1798.12
  4808.3 1797.89  4852.1 1793.65  4902.1 1792.40  4937.5 1792.26  4958.3 1794.95
  4991.7 1791.62  5103.2 1790.93  5103.7 1790.43  5115.1 1790.93  5157.3 1792.01
  5171.6 1795.32  5213.2 1797.02  5233.3 1800.57  5296.4 1805.85  5358.8 1807.92
#Mann=8,-1,0
  4494.8    0.07       0  4528.5     0.1       0  4654.8   0.035       0
  4730.4     0.1       0  4991.7    0.07       0  5103.2    0.05       0
  5115.1    0.07       0  5233.3   0.035       0
Bank Sta=5103.2,5115.1
Exp/Cntr=0.3,0.1

Type RM Length L Ch R = 1,10640,424,424,424
BEGIN DESCRIPTION:
Henderson Branch 23.0
END DESCRIPTION:
XS GIS Cut Line= 3
      1891264.12     13952174.72      1890665.23     13952299.62
      1890152.23     13952589.68
#Sta/Elev= 30
  4377.6 1927.45  4408.0 1916.47  4427.8 1904.87  4444.8 1891.65  4452.9 1888.15
  4458.4 1880.51  4468.6 1872.61  4502.9 1853.92  4509.5 1847.17  4519.7 1840.89
  4546.2 1827.35  4597.9 1809.25  4611.7 1807.18  4632.1 1808.96  4647.7 1804.61
  4749.1 1798.12  4850.5 1795.78  4887.5 1795.49  4911.6 1791.36  5052.8 1791.00
  5083.6 1790.93  5084.1 1790.43  5095.5 1790.93  5139.0 1791.15  5192.1 1795.79
  5235.3 1798.37  5251.2 1804.46  5265.3 1805.49  5337.8 1805.36  5578.7 1812.43
#Mann=11,-1,0
  4377.6     0.1       0  4444.8    0.07       0  4546.2     0.1       0
  4647.7   0.035       0  4749.1    0.07       0  4850.5     0.1       0
  4911.6    0.07       0  5052.8     0.1       0  5083.6    0.05       0
  5095.5     0.1       0  5192.1   0.035       0
Bank Sta=5083.6,5095.5
Exp/Cntr=0.3,0.1

Type RM Length L Ch R = 1,10216,282,282,282
BEGIN DESCRIPTION:
Henderson Branch 22.0
END DESCRIPTION:
XS GIS Cut Line= 4
      1891260.43     13952042.50      1890802.13     13951893.70
      1890386.51     13952120.49      1890120.81     13952372.76
#Sta/Elev= 30
  4180.5 1900.70  4190.0 1898.61  4216.7 1899.39  4248.7 1893.61  4280.9 1874.68
  4285.9 1873.50  4291.3 1867.67  4312.4 1856.85  4317.9 1851.80  4323.1 1851.66
  4349.8 1834.89  4355.1 1834.61  4381.8 1824.60  4387.0 1826.44  4413.8 1817.30
  4419.0 1817.77  4438.5 1813.07  4482.9 1813.79  4533.2 1805.50  4658.2 1798.97
  4849.7 1792.61  4898.6 1792.00  4899.1 1791.50  4910.6 1792.00  4926.4 1792.29
  4964.4 1797.57  5054.7 1797.88  5140.3 1797.15  5246.3 1802.08  5502.2 1807.78
#Mann=6,-1,0
  4180.5     0.1       0  4280.9    0.07       0  4849.7     0.1       0
  4898.6    0.05       0  4910.6     0.1       0  5054.7   0.035       0
Bank Sta=4898.6,4910.6
Exp/Cntr=0.3,0.1

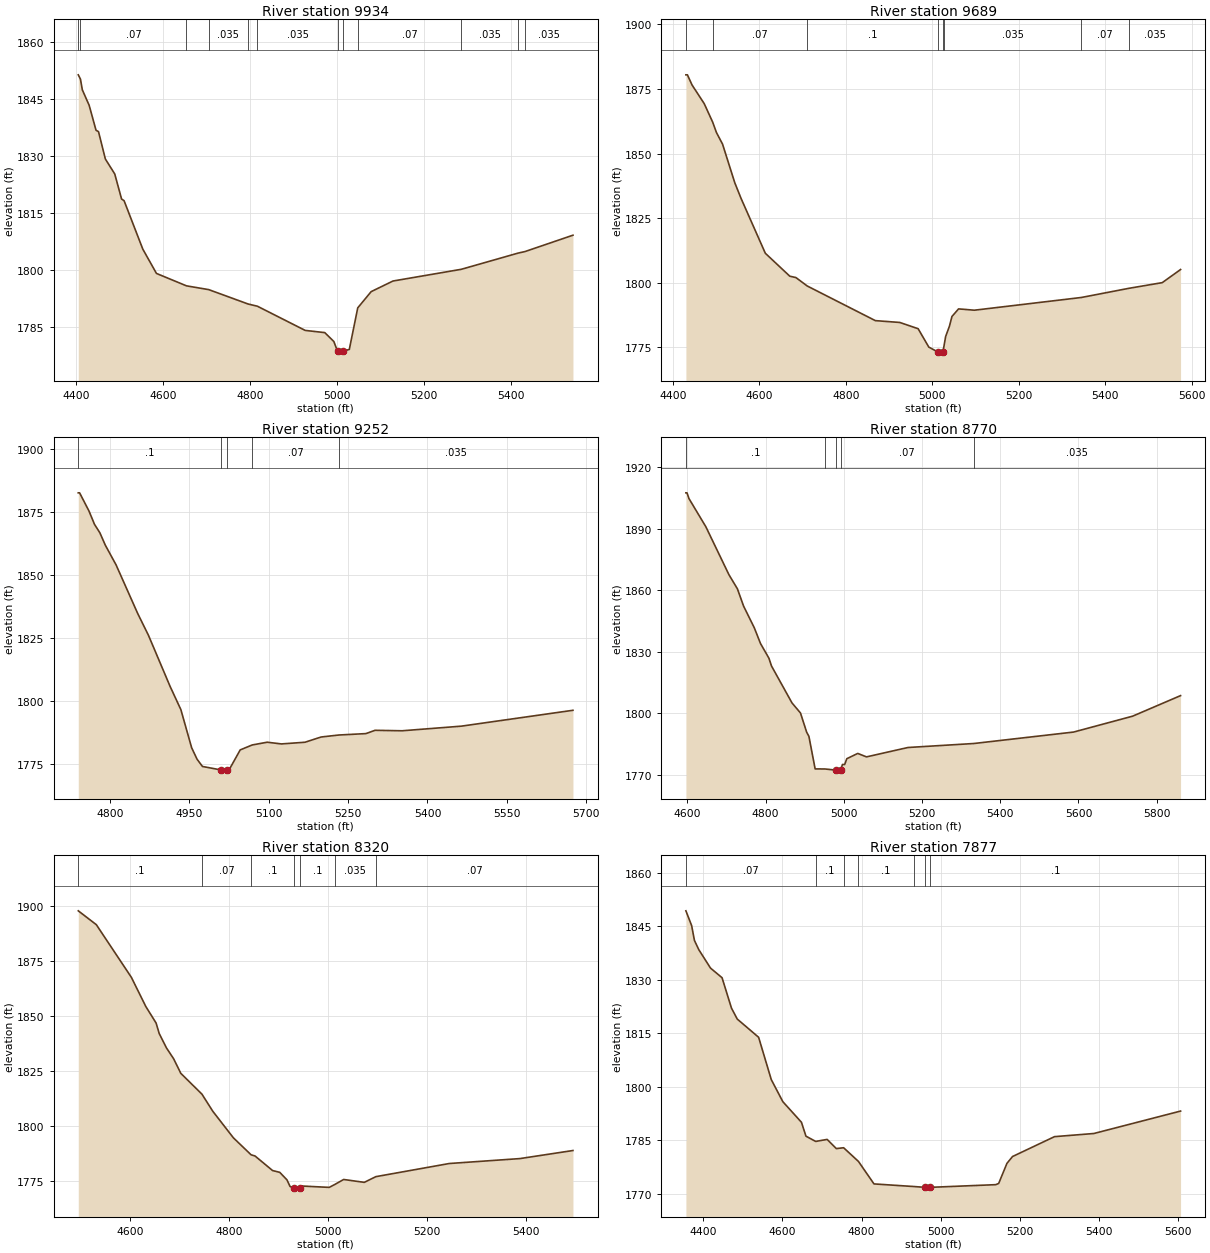
Type RM Length L Ch R = 1,9934,245,245,245
BEGIN DESCRIPTION:
Henderson Branch 21.1
END DESCRIPTION:
XS GIS Cut Line= 3
      1890621.76     13951356.94      1890358.74     13951808.76
      1889996.77     13952304.84
#Sta/Elev= 30
  4405.6 1851.37  4410.6 1850.24  4414.9 1847.42  4430.6 1843.34  4446.4 1836.76
  4452.1 1836.39  4467.9 1829.17  4489.4 1825.24  4505.1 1818.64  4510.9 1818.18
  4553.9 1805.42  4585.3 1799.01  4654.2 1795.74  4705.5 1794.74  4795.9 1790.95
  4817.2 1790.37  4927.1 1783.99  4972.1 1783.41  4993.0 1781.06  5001.4 1778.50
  5001.9 1778.00  5013.9 1778.50  5028.5 1778.97  5047.9 1789.93  5078.7 1794.21
  5128.9 1797.01  5285.9 1800.10  5416.8 1804.38  5432.4 1804.78  5542.5 1809.09
#Mann=12,-1,0
  4405.6     0.1       0  4410.6    0.07       0  4654.2     0.1       0
  4705.5   0.035       0  4795.9    0.07       0  4817.2   0.035       0
  5001.4   0.035       0  5013.9   0.035       0  5047.9    0.07       0
  5285.9   0.035       0  5416.8    0.07       0  5432.4   0.035       0
Bank Sta=5001.4,5013.9
Exp/Cntr=0.3,0.1

Type RM Length L Ch R = 1,9689,437,437,437
BEGIN DESCRIPTION:
Henderson Branch 21.0
END DESCRIPTION:
XS GIS Cut Line= 3
      1890574.98     13951275.02      1890175.00     13951675.00
      1889867.15     13952165.42
#Sta/Elev= 30
  4429.8 1880.49  4433.3 1880.49  4443.9 1876.60  4472.2 1869.33  4491.9 1862.11
  4500.5 1858.13  4514.6 1853.66  4542.9 1838.69  4557.1 1832.75  4613.6 1811.36
  4670.2 1802.48  4684.3 1801.95  4710.7 1798.67  4868.2 1785.26  4924.8 1784.55
  4967.2 1782.13  4991.9 1775.01  5012.2 1773.17  5012.7 1772.67  5024.7 1773.17
  5028.2 1776.54  5030.9 1779.14  5039.6 1783.08  5045.5 1786.88  5060.8 1789.81
  5097.4 1789.30  5344.9 1794.23  5454.6 1797.77  5532.1 1799.98  5574.5 1805.06
#Mann=8,-1,0
  4429.8     0.1       0  4491.9    0.07       0  4710.7     0.1       0
  5012.2    0.05       0  5024.7     0.1       0  5028.2   0.035       0
  5344.9    0.07       0  5454.6   0.035       0
Bank Sta=5012.2,5024.7
Exp/Cntr=0.3,0.1

Type RM Length L Ch R = 1,9252,482,482,482
BEGIN DESCRIPTION:
Henderson Branch 20.0
END DESCRIPTION:
XS GIS Cut Line= 3
      1889975.00     13951125.00      1889925.00     13951375.00
      1889794.44     13952041.79
#Sta/Elev= 30
  4740.4 1882.74  4742.9 1882.74  4760.8 1875.45  4771.0 1870.24  4781.2 1866.87
  4791.4 1861.99  4811.8 1854.13  4852.6 1834.85  4873.0 1826.15  4913.8 1805.90
  4934.2 1796.65  4954.6 1781.48  4964.8 1776.96  4975.0 1774.08  5009.4 1772.73
  5009.9 1772.23  5022.0 1772.73  5026.2 1773.10  5046.3 1780.66  5069.0 1782.62
  5097.2 1783.71  5124.1 1783.03  5168.6 1783.70  5199.1 1785.78  5232.6 1786.57
  5283.7 1787.13  5301.0 1788.44  5352.0 1788.25  5464.1 1790.09  5674.8 1796.39
#Mann=5,-1,0
  4740.4     0.1       0  5009.4    0.05       0  5022.0     0.1       0
  5069.0    0.07       0  5232.6   0.035       0
Bank Sta=5009.4,5022
Exp/Cntr=0.3,0.1

Type RM Length L Ch R = 1,8770,450,450,450
BEGIN DESCRIPTION:
Henderson Branch 19.0
END DESCRIPTION:
XS GIS Cut Line= 3
      1889674.98     13950925.04      1889475.00     13951275.00
      1889087.46     13952044.44
#Sta/Elev= 30
  4596.5 1907.43  4599.3 1907.43  4604.4 1904.61  4647.6 1890.85  4706.6 1867.47
  4728.2 1860.60  4744.0 1852.17  4771.4 1841.58  4787.2 1833.94  4808.8 1826.75
  4815.3 1822.98  4867.8 1804.93  4889.4 1800.05  4905.3 1790.64  4911.0 1788.64
  4926.9 1772.76  4952.0 1772.73  4979.6 1772.18  4980.1 1771.68  4992.2 1772.18
  4996.7 1774.92  5002.4 1774.92  5007.9 1777.74  5035.8 1780.31  5058.2 1778.63
  5164.1 1783.20  5332.4 1785.15  5587.4 1790.73  5738.6 1798.49  5861.1 1808.51
#Mann=5,-1,0
  4596.5     0.1       0  4952.0    0.07       0  4979.6    0.05       0
  4992.2    0.07       0  5332.4   0.035       0
Bank Sta=4979.6,4992.2
Exp/Cntr=0.3,0.1

Type RM Length L Ch R = 1,8320,443,443,443
BEGIN DESCRIPTION:
Henderson Branch 18.0
END DESCRIPTION:
XS GIS Cut Line= 3
      1889475.03     13950824.98      1889075.00     13951125.00
      1888775.02     13951524.97
#Sta/Elev= 30
  4495.2 1897.65  4531.7 1891.37  4602.5 1867.52  4631.7 1854.30  4652.5 1846.79
  4658.8 1842.05  4673.4 1835.54  4687.9 1830.62  4702.5 1823.99  4745.2 1814.56
  4767.1 1806.81  4808.8 1794.76  4844.6 1787.06  4852.5 1786.54  4887.9 1779.94
  4902.5 1779.12  4917.1 1775.70  4923.4 1772.69  4931.6 1772.01  4932.1 1771.51
  4944.3 1772.01  4945.2 1772.94  5002.5 1772.30  5013.3 1773.57  5031.7 1775.88
  5073.4 1774.58  5096.7 1777.16  5245.2 1783.12  5387.9 1785.35  5495.2 1789.01
#Mann=7,-1,0
  4495.2     0.1       0  4745.2    0.07       0  4844.6     0.1       0
  4931.6    0.05       0  4944.3     0.1       0  5013.3   0.035       0
  5096.7    0.07       0
Bank Sta=4931.6,4944.3
Exp/Cntr=0.3,0.1

Type RM Length L Ch R = 1,7877,420,420,420
BEGIN DESCRIPTION:
Henderson Branch 17.0
END DESCRIPTION:
XS GIS Cut Line= 3
      1889274.98     13950725.01      1888675.00     13950975.00
      1888224.97     13951375.03
#Sta/Elev= 30
  4355.5 1849.34  4370.1 1845.18  4377.1 1841.05  4388.0 1838.48  4417.8 1833.29
  4447.0 1830.59  4470.9 1822.06  4485.5 1819.00  4539.6 1813.89  4571.6 1802.04
  4600.9 1795.84  4648.0 1790.07  4659.4 1786.17  4684.1 1784.70  4713.0 1785.27
  4736.3 1782.69  4754.7 1782.93  4792.3 1779.09  4831.6 1772.79  4932.2 1772.06
  4960.4 1771.83  4960.9 1771.33  4973.6 1771.83  5139.7 1772.58  5147.2 1772.92
  5168.1 1778.55  5182.3 1780.47  5288.5 1786.04  5388.0 1786.92  5607.6 1793.21
#Mann=7,-1,0
  4355.5    0.07       0  4684.1     0.1       0  4754.7    0.07       0
  4792.3     0.1       0  4932.2    0.07       0  4960.4    0.05       0
  4973.6     0.1       0
Bank Sta=4960.4,4973.6
Exp/Cntr=0.3,0.1

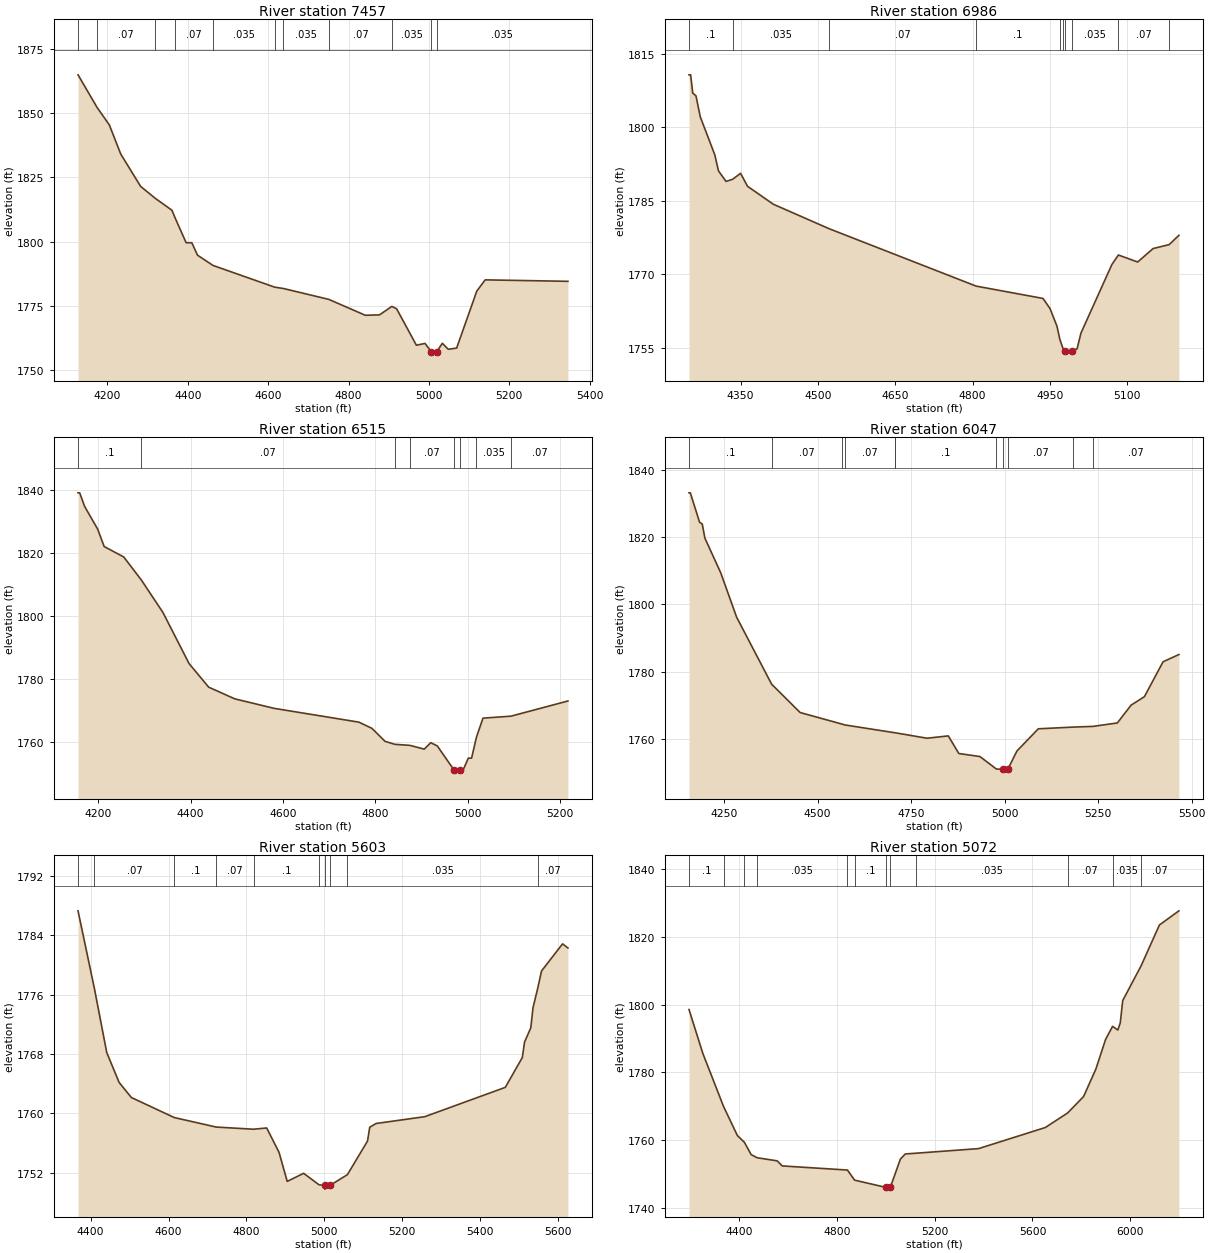
Type RM Length L Ch R = 1,7457,471,471,471
BEGIN DESCRIPTION:
Henderson Branch 16.0
END DESCRIPTION:
XS GIS Cut Line= 3
      1889025.02     13950024.98      1888429.46     13950656.00
      1888146.45     13950863.49
#Sta/Elev= 30
  4127.2 1864.96  4174.7 1852.24  4205.1 1845.46  4233.4 1834.14  4282.8 1821.56
  4318.8 1816.95  4360.9 1812.23  4368.7 1809.25  4396.1 1799.61  4410.2 1799.60
  4424.4 1794.76  4462.9 1790.77  4616.2 1782.32  4638.2 1781.78  4751.0 1777.55
  4841.9 1771.36  4877.1 1771.52  4907.8 1774.81  4919.6 1773.91  4968.9 1759.71
  4990.4 1760.41  5005.9 1757.13  5006.4 1756.63  5019.3 1757.13  5033.4 1760.45
  5048.1 1758.13  5069.0 1758.59  5119.1 1780.78  5140.0 1785.15  5345.8 1784.58
#Mann=11,-1,0
  4127.2     0.1       0  4174.7    0.07       0  4318.8     0.1       0
  4368.7    0.07       0  4462.9   0.035       0  4616.2    0.07       0
  4638.2   0.035       0  4751.0    0.07       0  4907.8   0.035       0
  5005.9   0.035       0  5019.3   0.035       0
Bank Sta=5005.9,5019.3
Exp/Cntr=0.3,0.1

Type RM Length L Ch R = 1,6986,471,471,471
BEGIN DESCRIPTION:
Henderson Branch 15.0
END DESCRIPTION:
XS GIS Cut Line= 3
      1888674.96     13949925.03      1888075.00     13950375.00
      1888075.00     13950575.05
#Sta/Elev= 30
  4250.0 1810.74  4253.1 1810.74  4257.2 1807.01  4263.5 1806.45  4271.8 1802.17
  4300.0 1794.40  4307.2 1791.11  4321.8 1788.97  4334.6 1789.41  4350.0 1790.62
  4363.5 1787.97  4413.5 1784.31  4521.5 1779.32  4806.7 1767.59  4936.4 1765.07
  4950.0 1763.02  4963.5 1759.41  4969.1 1756.72  4975.0 1754.91  4979.7 1754.40
  4980.2 1753.90  4993.1 1754.40  5002.5 1754.76  5010.0 1757.98  5070.0 1771.99
  5082.6 1773.94  5120.0 1772.51  5150.0 1775.26  5181.0 1776.06  5200.0 1777.96
#Mann=10,-1,0
  4250.0     0.1       0  4334.6   0.035       0  4521.5    0.07       0
  4806.7     0.1       0  4969.1    0.07       0  4975.0   0.035       0
  4979.7   0.035       0  4993.1   0.035       0  5082.6    0.07       0
  5181.0   0.035       0
Bank Sta=4979.7,4993.1
Exp/Cntr=0.3,0.1

Type RM Length L Ch R = 1,6515,468,468,468
BEGIN DESCRIPTION:
Henderson Branch 14.0
END DESCRIPTION:
XS GIS Cut Line= 3
      1888325.02     13949474.98      1887725.00     13950075.00
      1887574.99     13950225.01
#Sta/Elev= 30
  4156.1 1839.09  4159.7 1839.09  4170.3 1834.81  4198.5 1827.61  4212.7 1822.06
  4255.1 1818.75  4293.2 1811.45  4340.0 1801.14  4396.5 1784.96  4439.0 1777.47
  4495.5 1773.77  4580.4 1770.76  4764.2 1766.38  4792.5 1764.41  4820.8 1760.30
  4841.8 1759.35  4874.6 1759.02  4905.7 1757.83  4919.8 1759.86  4933.9 1758.85
  4969.5 1751.35  4970.0 1750.85  4983.2 1751.35  4990.5 1751.41  5001.1 1754.96
  5008.2 1754.96  5018.7 1761.61  5032.9 1767.65  5093.4 1768.27  5216.8 1773.09
#Mann=8,-1,0
  4156.1     0.1       0  4293.2    0.07       0  4841.8     0.1       0
  4874.6    0.07       0  4969.5    0.05       0  4983.2    0.07       0
  5018.7   0.035       0  5093.4    0.07       0
Bank Sta=4969.5,4983.2
Exp/Cntr=0.3,0.1

Type RM Length L Ch R = 1,6047,444,444,444
BEGIN DESCRIPTION:
Henderson Branch 13.0
END DESCRIPTION:
XS GIS Cut Line= 3
      1888124.99     13949075.01      1887525.00     13949675.00
      1887174.99     13949975.01
#Sta/Elev= 30
  4156.5 1833.13  4160.0 1833.13  4184.8 1824.37  4191.8 1823.91  4198.9 1819.69
  4241.3 1809.39  4283.8 1796.22  4377.3 1776.35  4453.5 1767.94  4564.3 1764.54
  4573.4 1764.25  4708.2 1761.91  4708.4 1761.91  4792.9 1760.31  4849.5 1761.01
  4877.7 1755.78  4934.3 1754.87  4977.7 1751.20  4994.6 1751.05  4995.1 1750.55
  5008.4 1751.05  5033.0 1756.52  5090.1 1763.11  5184.0 1763.62  5236.0 1763.82
  5301.4 1764.84  5338.1 1770.12  5373.8 1772.65  5423.7 1783.00  5466.0 1785.15
#Mann=11,-1,0
  4156.5     0.1       0  4377.3    0.07       0  4564.3   0.035       0
  4573.4    0.07       0  4708.2   0.035       0  4708.4     0.1       0
  4977.7    0.07       0  4994.6    0.05       0  5008.4    0.07       0
  5184.0   0.035       0  5236.0    0.07       0
Bank Sta=4994.6,5008.4
Exp/Cntr=0.3,0.1

Type RM Length L Ch R = 1,5603,531,531,531
BEGIN DESCRIPTION:
Henderson Branch 12.0
END DESCRIPTION:
XS GIS Cut Line= 3
      1887975.05     13949074.98      1887375.00     13949275.00
      1887075.00     13949825.00
#Sta/Elev= 30
  4367.5 1787.28  4409.8 1776.76  4441.3 1768.19  4473.0 1764.17  4504.6 1762.13
  4614.9 1759.43  4722.8 1758.15  4818.6 1757.86  4852.4 1758.03  4884.1 1754.74
  4905.1 1750.83  4947.3 1751.92  4987.0 1750.37  5001.2 1750.29  5001.7 1749.79
  5015.0 1750.29  5059.8 1751.74  5111.5 1756.27  5117.2 1758.13  5133.4 1758.63
  5258.7 1759.55  5465.6 1763.50  5509.3 1767.52  5515.0 1769.60  5531.1 1771.52
  5536.8 1774.24  5549.0 1776.87  5558.6 1779.17  5612.7 1782.83  5626.5 1782.28
#Mann=10,-1,0
  4367.5     0.1       0  4409.8    0.07       0  4614.9     0.1       0
  4722.8    0.07       0  4818.6     0.1       0  4987.0    0.07       0
  5001.2    0.05       0  5015.0    0.07       0  5059.8   0.035       0
  5549.0    0.07       0
Bank Sta=5001.2,5015
Exp/Cntr=0.3,0.1

Type RM Length L Ch R = 1,5072,382,382,382
BEGIN DESCRIPTION:
Henderson Branch 11.0
END DESCRIPTION:
XS GIS Cut Line= 3
      1887875.03     13948324.97      1887402.63     13948811.30
      1886075.02     13948775.00
#Sta/Elev= 30
  4193.7 1798.54  4250.2 1785.61  4335.0 1769.95  4391.7 1761.35  4420.5 1759.35
  4448.3 1755.71  4472.9 1754.79  4554.5 1753.88  4575.6 1752.38  4842.4 1751.16
  4871.9 1748.18  5000.8 1746.03  5001.3 1745.53  5017.9 1746.03  5059.4 1754.41
  5079.4 1755.91  5123.0 1756.13  5379.5 1757.49  5652.8 1763.72  5744.3 1768.02
  5809.7 1772.89  5859.7 1780.97  5899.7 1789.74  5928.1 1793.58  5949.7 1792.50
  5959.7 1794.62  5969.7 1801.20  6044.8 1811.42  6119.8 1823.48  6199.8 1827.68
#Mann=12,-1,0
  4193.7     0.1       0  4335.0   0.035       0  4420.5    0.07       0
  4472.9   0.035       0  4842.4    0.07       0  4871.9     0.1       0
  5000.8    0.05       0  5017.9     0.1       0  5123.0   0.035       0
  5744.3    0.07       0  5928.1   0.035       0  6044.8    0.07       0
Bank Sta=5000.8,5017.9
Exp/Cntr=0.3,0.1

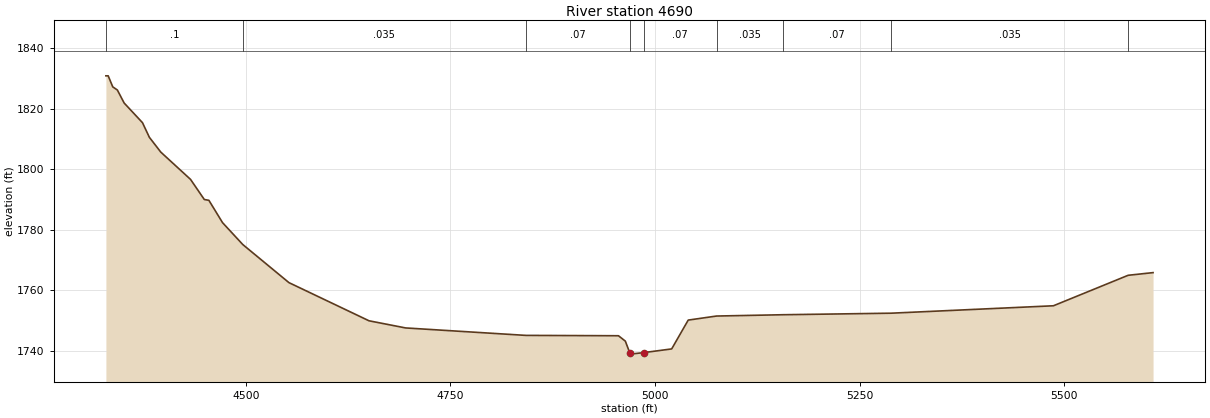
Type RM Length L Ch R = 1,4690,445,445,445
BEGIN DESCRIPTION:
Henderson Branch 10.0
END DESCRIPTION:
XS GIS Cut Line= 3
      1887924.98     13948175.01      1887325.00     13948475.00
      1886724.97     13948375.00
#Sta/Elev= 30
  4329.2 1830.86  4332.0 1830.86  4337.6 1827.21  4343.2 1826.18  4351.5 1821.88
  4373.9 1815.38  4382.3 1810.55  4396.3 1805.65  4432.6 1796.65  4449.4 1790.01
  4455.0 1789.74  4471.7 1782.36  4496.4 1775.14  4552.8 1762.55  4650.6 1749.95
  4695.3 1747.59  4842.1 1745.13  4955.3 1745.01  4963.7 1743.23  4969.0 1739.44
  4969.5 1738.94  4986.2 1739.44  5020.3 1740.66  5040.5 1750.18  5075.1 1751.52
  5156.1 1751.95  5288.4 1752.46  5486.6 1754.91  5577.9 1764.98  5608.3 1765.86
#Mann=9,-1,0
  4329.2     0.1       0  4496.4   0.035       0  4842.1    0.07       0
  4969.0    0.05       0  4986.2    0.07       0  5075.1   0.035       0
  5156.1    0.07       0  5288.4   0.035       0  5577.9    0.07       0
Bank Sta=4969,4986.2
Exp/Cntr=0.3,0.1