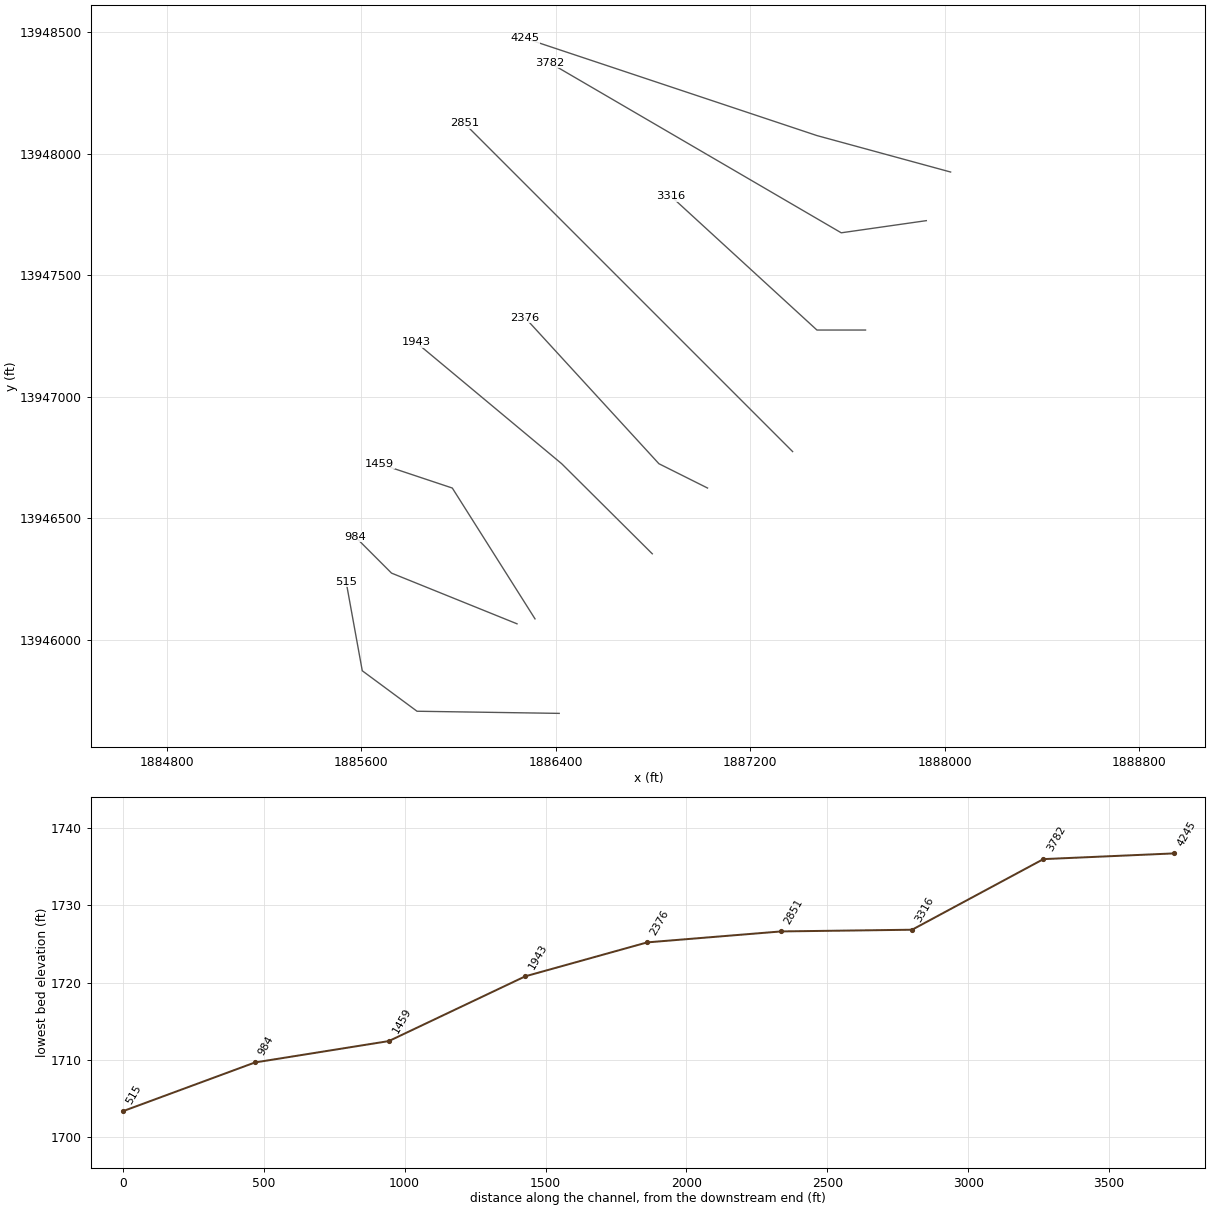
HEC-RAS study Henderson Branch.prj: Henderson Branch Base Level Engineering

--- Henderson Branch.g01 (geometry) --- (continued)

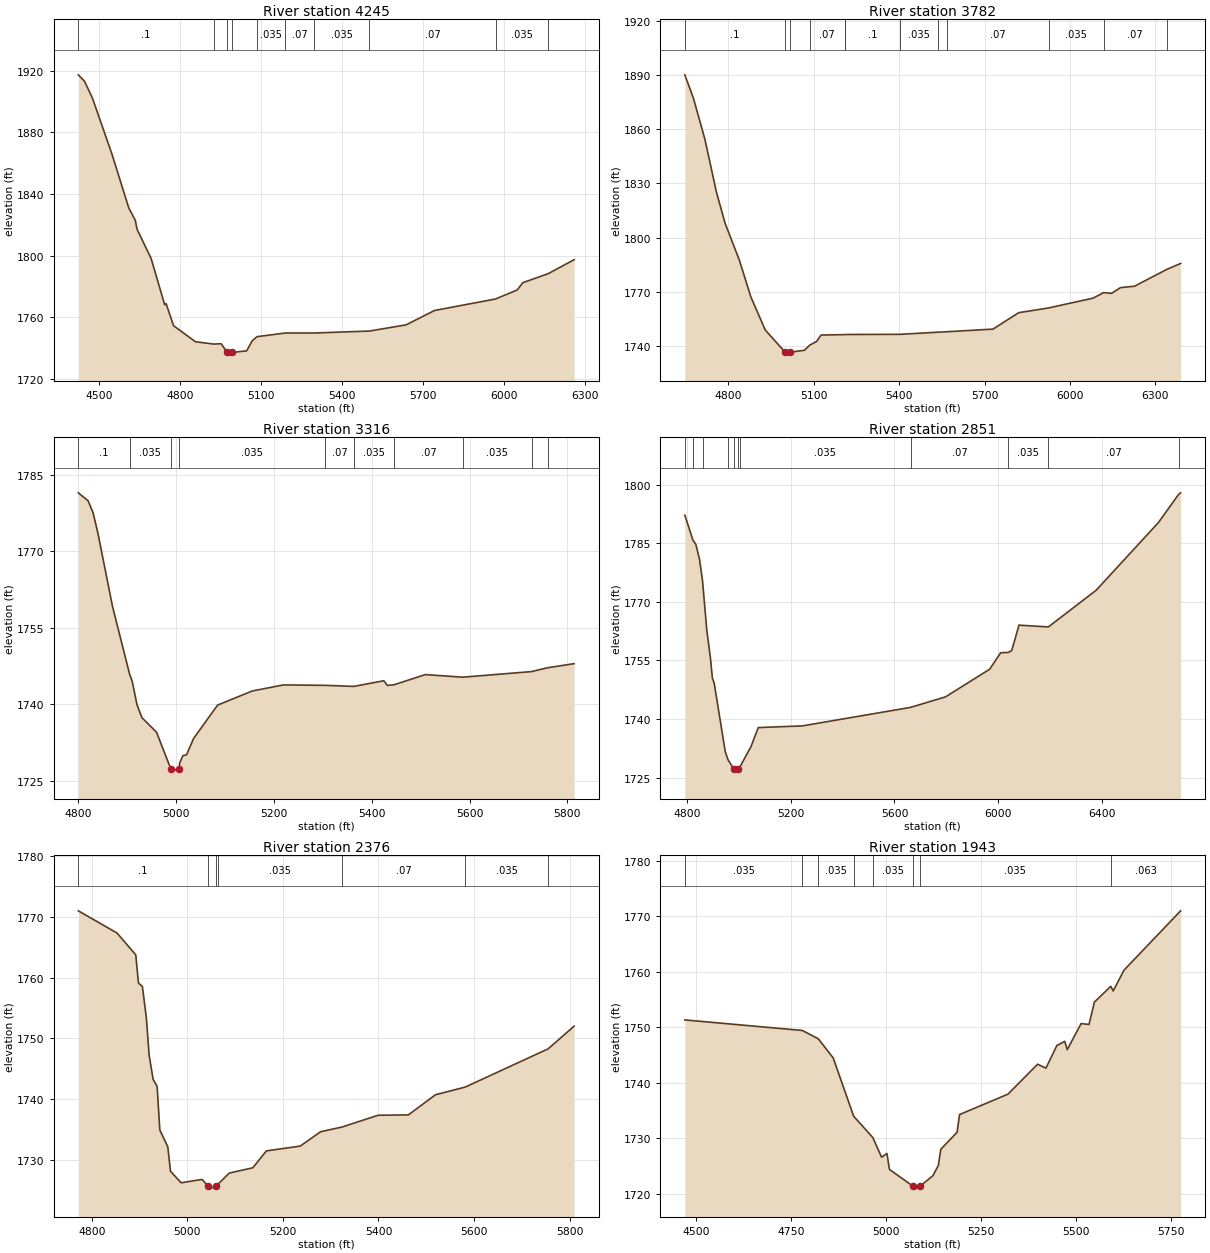
Type RM Length L Ch R = 1,4245,463,463,463
BEGIN DESCRIPTION:
Henderson Branch 9.0
END DESCRIPTION:
XS GIS Cut Line= 3
      1888024.98     13947925.01      1887475.00     13948075.00
      1886274.98     13948475.01
#Sta/Elev= 30
  4424.1 1917.36  4446.5 1913.30  4475.9 1902.48  4548.5 1865.93  4610.7 1831.03
  4634.8 1822.95  4641.7 1817.06  4693.6 1798.14  4743.7 1768.11  4748.9 1768.97
  4776.5 1754.56  4857.7 1744.12  4925.3 1742.63  4952.7 1742.84  4975.2 1737.25
  4975.7 1736.75  4992.4 1737.25  5046.9 1738.19  5068.0 1744.81  5085.6 1747.44
  5190.7 1749.81  5295.7 1749.80  5501.5 1751.08  5637.2 1755.10  5742.6 1764.43
  5968.4 1771.89  6048.3 1777.73  6069.3 1782.45  6163.7 1788.37  6259.1 1797.39
#Mann=10,-1,0
  4424.1     0.1       0  4925.3    0.07       0  4975.2    0.05       0
  4992.4    0.07       0  5085.6   0.035       0  5190.7    0.07       0
  5295.7   0.035       0  5501.5    0.07       0  5968.4   0.035       0
  6163.7    0.07       0
Bank Sta=4975.2,4992.4
Exp/Cntr=0.3,0.1

Type RM Length L Ch R = 1,3782,466,466,466
BEGIN DESCRIPTION:
Henderson Branch 8.0
END DESCRIPTION:
XS GIS Cut Line= 3
      1887925.00     13947725.00      1887575.00     13947675.00
      1886375.00     13948375.00
#Sta/Elev= 30
  4646.6 1890.04  4676.9 1877.09  4717.3 1854.30  4757.7 1825.13  4788.0 1807.97
  4838.5 1787.38  4878.9 1767.03  4929.4 1748.80  4999.4 1736.51  4999.9 1736.01
  5016.6 1736.51  5066.7 1737.58  5086.2 1740.49  5109.7 1742.45  5125.4 1746.01
  5208.1 1746.24  5210.1 1746.32  5403.4 1746.42  5537.0 1747.60  5569.6 1747.87
  5729.9 1749.30  5820.1 1758.39  5925.7 1761.03  6082.2 1766.47  6118.7 1769.51
  6146.7 1769.10  6178.1 1772.27  6227.3 1773.04  6340.6 1782.33  6389.4 1785.65
#Mann=12,-1,0
  4646.6     0.1       0  4999.4    0.05       0  5016.6     0.1       0
  5086.2    0.07       0  5208.1   0.035       0  5210.1     0.1       0
  5403.4   0.035       0  5537.0     0.1       0  5569.6    0.07       0
  5925.7   0.035       0  6118.7    0.07       0  6340.6   0.035       0
Bank Sta=4999.4,5016.6
Exp/Cntr=0.3,0.1

Type RM Length L Ch R = 1,3316,465,465,465
BEGIN DESCRIPTION:
Henderson Branch 7.0
END DESCRIPTION:
XS GIS Cut Line= 3
      1887675.01     13947275.00      1887475.00     13947275.00
      1886875.04     13947824.97
#Sta/Elev= 30
  4800.0 1781.52  4820.0 1779.96  4830.0 1777.64  4840.0 1773.63  4870.0 1759.16
  4904.8 1745.92  4910.0 1744.58  4920.0 1739.90  4930.0 1737.36  4960.0 1734.49
  4988.9 1727.36  4989.4 1726.86  5006.2 1727.36  5007.1 1728.42  5013.9 1729.91
  5021.3 1730.05  5035.5 1733.24  5084.8 1739.83  5155.7 1742.60  5219.2 1743.79
  5304.9 1743.71  5363.2 1743.50  5424.6 1744.61  5432.0 1743.69  5445.6 1743.82
  5509.6 1745.82  5586.2 1745.31  5726.8 1746.41  5760.1 1747.17  5813.9 1747.97
#Mann=10,-1,0
  4800.0     0.1       0  4904.8   0.035       0  4988.9   0.035       0
  5006.2   0.035       0  5304.9    0.07       0  5363.2   0.035       0
  5445.6    0.07       0  5586.2   0.035       0  5726.8     0.1       0
  5760.1    0.07       0
Bank Sta=4988.9,5006.2
Exp/Cntr=0.3,0.1

Type RM Length L Ch R = 1,2851,475,475,475
BEGIN DESCRIPTION:
Henderson Branch 6.0
END DESCRIPTION:
XS GIS Cut Line= 3
      1887374.99     13946775.01      1887225.00     13946925.00
      1886024.99     13948125.01
#Sta/Elev= 30
  4792.7 1792.19  4824.4 1785.71  4835.1 1784.74  4849.3 1780.89  4860.8 1775.45
  4877.5 1762.64  4891.7 1755.43  4898.8 1750.46  4905.8 1749.18  4948.3 1731.67
  4959.2 1729.52  4982.0 1727.14  4982.5 1726.64  4999.3 1727.14  5004.8 1727.70
  5047.3 1732.89  5075.5 1737.79  5245.2 1738.22  5662.6 1742.97  5796.8 1745.66
  5966.5 1752.73  6008.9 1756.95  6037.3 1757.03  6051.3 1757.49  6079.6 1764.02
  6192.6 1763.56  6376.6 1772.95  6617.0 1790.33  6694.7 1797.55  6701.9 1797.90
#Mann=11,-1,0
  4792.7   0.035       0  4824.4    0.07       0  4860.8     0.1       0
  4959.2    0.07       0  4982.0    0.05       0  4999.3    0.07       0
  5004.8   0.035       0  5662.6    0.07       0  6037.3   0.035       0
  6192.6    0.07       0  6694.7   0.035       0
Bank Sta=4982,4999.3
Exp/Cntr=0.3,0.1

Type RM Length L Ch R = 1,2376,433,433,433
BEGIN DESCRIPTION:
Henderson Branch 5.0
END DESCRIPTION:
XS GIS Cut Line= 3
      1887024.99     13946625.01      1886825.00     13946725.00
      1886275.02     13947324.98
#Sta/Elev= 30
  4772.0 1771.00  4853.0 1767.35  4892.2 1763.76  4897.8 1759.13  4906.1 1758.55
  4914.5 1753.29  4920.1 1747.27  4928.5 1743.29  4936.9 1742.12  4942.5 1734.96
  4959.3 1732.16  4964.8 1728.17  4987.2 1726.26  5031.0 1726.82  5043.3 1725.72
  5043.8 1725.22  5060.7 1725.72  5064.8 1726.08  5087.8 1727.86  5137.1 1728.73
  5165.5 1731.51  5236.4 1732.30  5278.9 1734.66  5324.0 1735.44  5399.2 1737.37
  5462.7 1737.43  5519.4 1740.75  5581.4 1742.00  5755.0 1748.29  5809.5 1752.03
#Mann=7,-1,0
  4772.0     0.1       0  5043.3    0.05       0  5060.7     0.1       0
  5064.8   0.035       0  5324.0    0.07       0  5581.4   0.035       0
  5755.0    0.07       0
Bank Sta=5043.3,5060.7
Exp/Cntr=0.3,0.1

Type RM Length L Ch R = 1,1943,484,484,484
BEGIN DESCRIPTION:
Henderson Branch 4.0
END DESCRIPTION:
XS GIS Cut Line= 3
      1886797.70     13946354.49      1886425.00     13946725.00
      1885824.97     13947225.03
#Sta/Elev= 30
  4469.7 1751.30  4779.5 1749.40  4821.7 1747.89  4860.9 1744.43  4914.6 1733.96
  4965.3 1730.09  4988.2 1726.57  5002.4 1727.24  5008.9 1724.37  5071.7 1721.32
  5072.2 1720.82  5089.2 1721.32  5123.5 1723.24  5137.8 1725.08  5144.3 1728.00
  5187.2 1731.06  5193.7 1734.25  5321.3 1737.93  5399.4 1743.32  5421.5 1742.62
  5450.2 1746.70  5471.0 1747.44  5477.5 1745.95  5514.0 1750.64  5534.8 1750.48
  5549.1 1754.51  5592.3 1757.35  5598.6 1756.52  5627.2 1760.27  5776.3 1770.95
#Mann=8,-1,0
  4469.7   0.035       0  4779.5     0.1       0  4821.7   0.035       0
  4914.6     0.1       0  4965.3   0.035       0  5071.7   0.035       0
  5089.2   0.035       0  5592.3   0.063       0
Bank Sta=5071.7,5089.2
Exp/Cntr=0.3,0.1

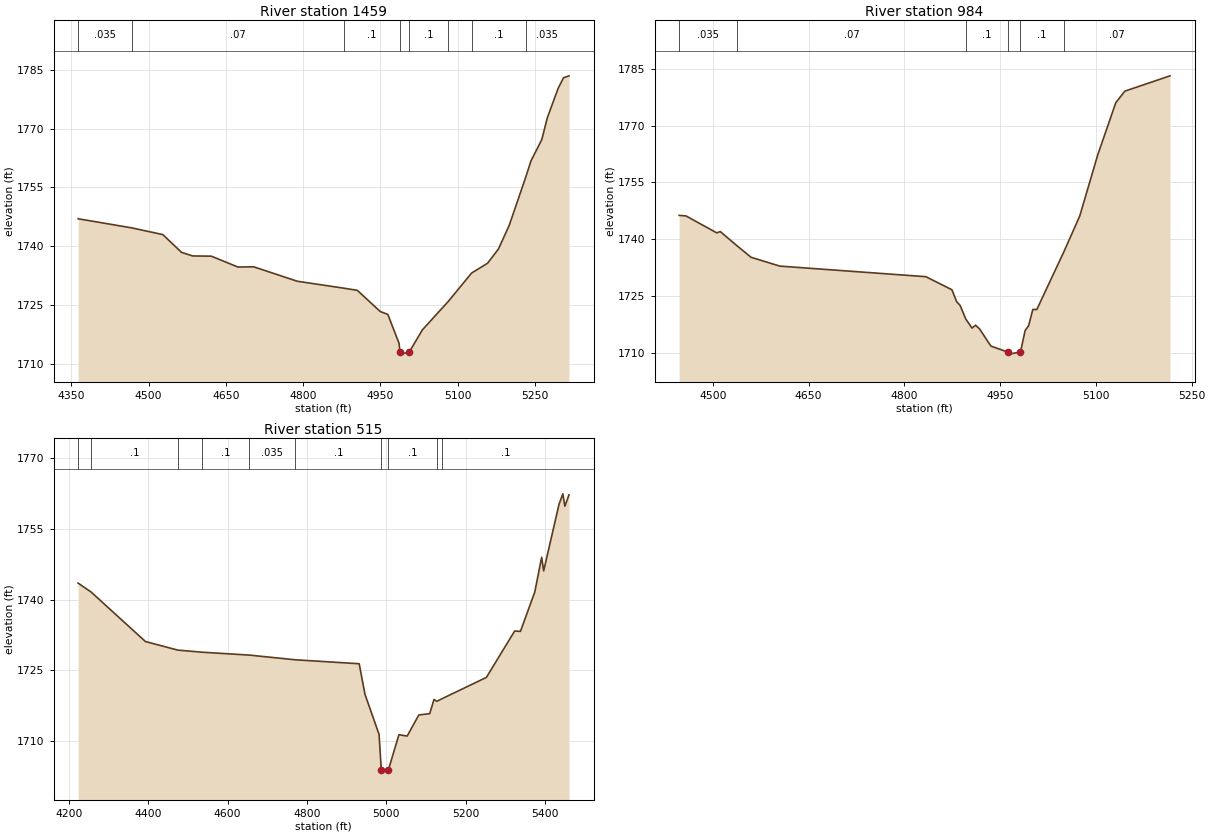
Type RM Length L Ch R = 1,1459,475,475,475
BEGIN DESCRIPTION:
Henderson Branch 3.0
END DESCRIPTION:
XS GIS Cut Line= 3
      1886315.25     13946086.79      1885975.00     13946625.00
      1885674.97     13946725.01
#Sta/Elev= 30
  4363.2 1747.00  4467.0 1744.68  4527.7 1742.96  4564.1 1738.41  4585.9 1737.50
  4621.8 1737.45  4673.5 1734.67  4704.1 1734.73  4788.8 1731.04  4879.8 1729.26
  4905.3 1728.72  4949.9 1723.30  4964.5 1722.58  4986.4 1715.17  4988.0 1712.93
  4988.5 1712.43  5006.0 1712.93  5031.6 1718.63  5082.1 1725.92  5127.1 1733.13
  5158.1 1735.63  5179.1 1739.24  5200.2 1745.32  5232.1 1757.56  5242.4 1761.77
  5263.5 1767.24  5274.0 1772.73  5295.1 1780.28  5305.6 1783.00  5316.2 1783.50
#Mann=8,-1,0
  4363.2   0.035       0  4467.0    0.07       0  4879.8     0.1       0
  4988.0    0.05       0  5006.0     0.1       0  5082.1    0.07       0
  5127.1     0.1       0  5232.1   0.035       0
Bank Sta=4988,5006
Exp/Cntr=0.3,0.1

Type RM Length L Ch R = 1,984,469,469,469
BEGIN DESCRIPTION:
Henderson Branch 2.0
END DESCRIPTION:
XS GIS Cut Line= 3
      1886241.21     13946066.45      1885725.00     13946275.00
      1885574.98     13946425.02
#Sta/Elev= 30
  4447.1 1746.28  4457.9 1746.13  4506.1 1741.66  4511.5 1742.01  4537.9 1738.24
  4559.8 1735.22  4604.8 1732.89  4833.5 1730.10  4874.4 1726.65  4881.8 1723.50
  4887.2 1722.53  4896.2 1718.89  4905.9 1716.54  4911.3 1717.29  4917.6 1716.34
  4935.4 1711.79  4962.5 1710.16  4963.0 1709.66  4980.5 1710.16  4982.3 1710.63
  4989.1 1715.92  4994.5 1717.14  5001.1 1721.45  5007.4 1721.45  5049.2 1736.47
  5074.6 1746.10  5102.8 1762.26  5131.1 1776.03  5145.3 1779.07  5216.0 1783.11
#Mann=6,-1,0
  4447.1   0.035       0  4537.9    0.07       0  4896.2     0.1       0
  4962.5    0.05       0  4980.5     0.1       0  5049.2    0.07       0
Bank Sta=4962.5,4980.5
Exp/Cntr=0.3,0.1

Type RM Length L Ch R = 1,515,0,0,0
BEGIN DESCRIPTION:
Henderson Branch 1.0
END DESCRIPTION:
XS GIS Cut Line= 4
      1886414.76     13945697.99      1885829.89     13945706.75
      1885604.64     13945873.26      1885538.06     13946239.82
#Sta/Elev= 30
  4222.9 1743.49  4255.5 1741.61  4392.7 1731.08  4474.1 1729.26  4535.7 1728.81
  4654.0 1728.20  4770.4 1727.20  4931.6 1726.36  4946.2 1719.87  4981.7 1711.35
  4987.3 1703.84  4987.8 1703.34  5005.3 1703.84  5031.8 1711.29  5052.6 1711.00
  5081.9 1715.48  5109.4 1715.76  5120.2 1718.77  5127.3 1718.38  5140.1 1718.92
  5252.3 1723.46  5323.5 1733.30  5338.2 1733.24  5374.3 1741.60  5391.6 1748.97
  5396.7 1746.08  5435.3 1760.19  5445.0 1762.45  5450.1 1759.82  5460.5 1762.22
#Mann=10,-1,0
  4222.9   0.035       0  4255.5     0.1       0  4474.1   0.035       0
  4535.7     0.1       0  4654.0   0.035       0  4770.4     0.1       0
  4987.3    0.05       0  5005.3     0.1       0  5127.3    0.07       0
  5140.1     0.1       0
Bank Sta=4987.3,5005.3
Exp/Cntr=0.3,0.1

Chan Stop Cuts=-1