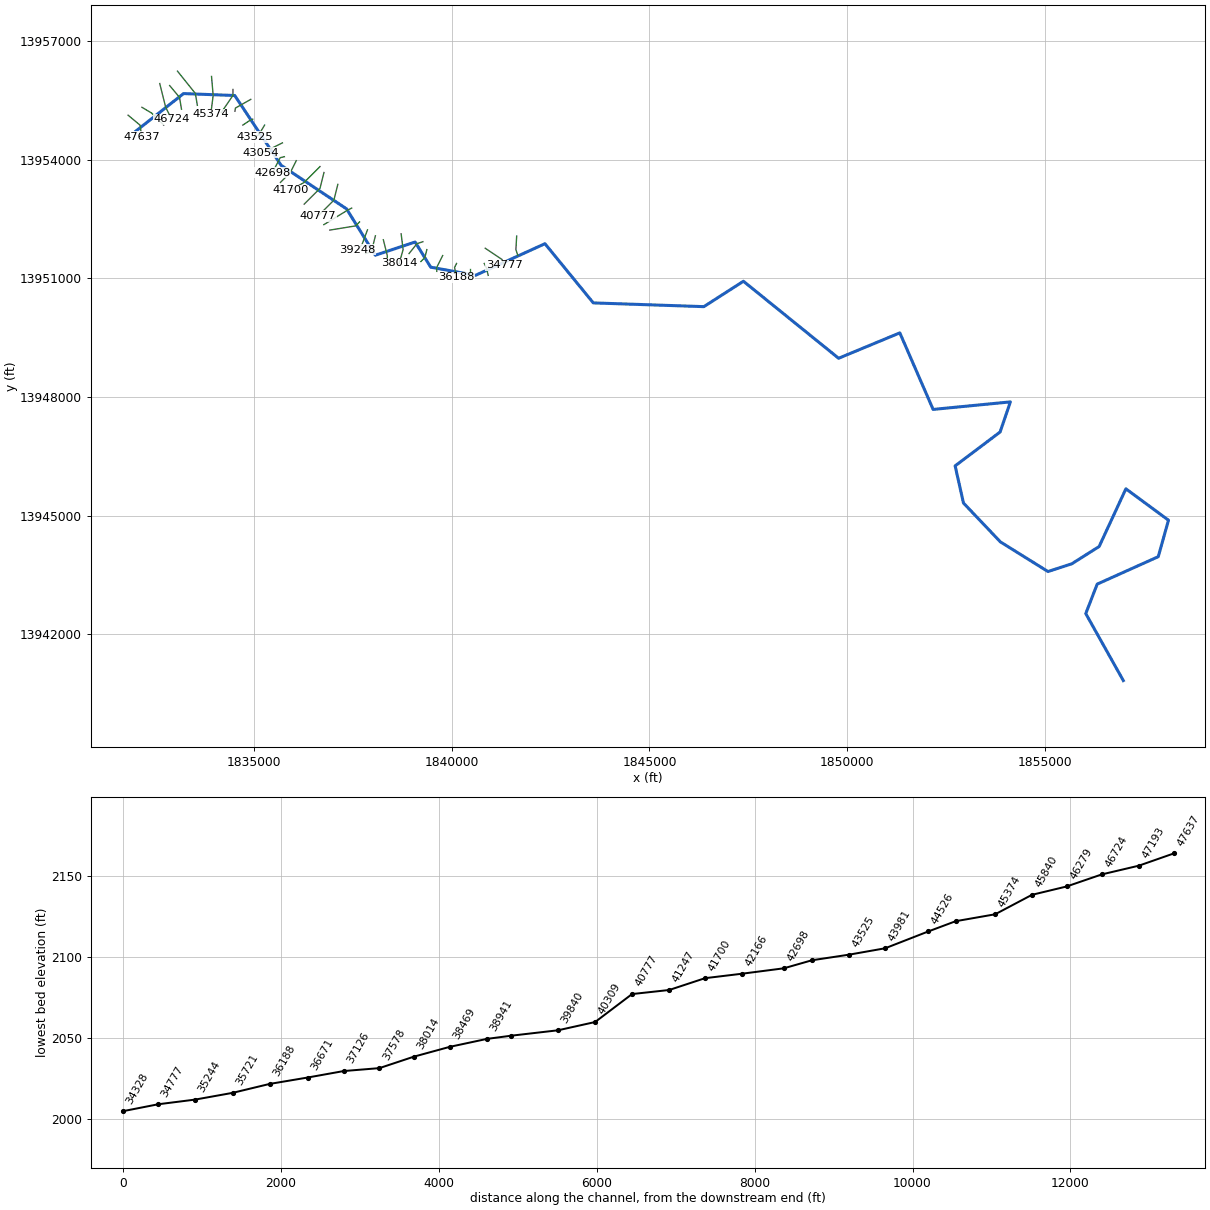
--- Honey Creek.prj (project) ---

Proj Title=Honey Creek Base Level Engineering
Current Plan=p01
Default Exp/Contr=0.3,0.1
English Units
Geom File=g01
Flow File=f01
Plan File=p01
BEGIN DESCRIPTION:
Honey Creek
END DESCRIPTION:

--- Honey Creek.p01 (plan) ---

Plan Title=Multiple Run
Short Identifier=Multiple
Geom File=g01
Flow File=f01
Subcritical Flow
K Sum by GR= 0
Std Step Tol= 0.01
Critical Tol= 0.01
Num of Std Step Trials= 20
Max Error Tol= 0.3
Flow Tol Ratio= 0.001
Split Flow NTrial= 30
Split Flow Tol= 0.02
Split Flow Ratio= 0.02
Log Output Level= 0
Friction Slope Method= 1
Unsteady Friction Slope Method= 2
Unsteady Bridges Friction Slope Method= 1
Parabolic Critical Depth
Global Vel Dist=  1 , 1 , 1
Global Log Level= 0
CheckData=True
Encroach Param= -1, 0, 0, 0
BEGIN DESCRIPTION:
Multiple Run
END DESCRIPTION:

--- Honey Creek.f01 (steady flow) ---

Flow Title=Multiple
Number of Profiles=7
Profile Names=10-year,25-year,50-year,1pct_min,100-year,1pct_plu,500-year
River Rch & RM= Honey Creek,Reach-1,47637
     491     797    1074     702    1401    2795    2348
River Rch & RM= Honey Creek,Reach-1,45840
    1156    1979    2764    1864    3719    7420    6656
River Rch & RM= Honey Creek,Reach-1,41247
    1776    3114    4418    3023    6032   12035   11122
River Rch & RM= Honey Creek,Reach-1,38469
    2139    3784    5400    3713    7409   14783   13803
River Rch & RM= Honey Creek,Reach-1,35721
    2573    4591    6589    4554    9087   18131   17105
River Rch & RM= Honey Creek,Reach-1,34328
    3058    5503    7943    5519   11013   21973   20952
River Rch & RM= Honey Creek,Reach-1,33366
    3203    5766    8325    5783   11539   23023   21946
River Rch & RM= Honey Creek,Reach-1,30164
    3669    6638    9617    6700   13369   26675   25577
River Rch & RM= Honey Creek,Reach-1,27911
    3876    7032   10206    7122   14211   28355   27279
River Rch & RM= Honey Creek,Reach-1,26965
    4693    8575   12505    8764   17487   34891   33852
River Rch & RM= Honey Creek,Reach-1,21101
    5228    9551   13931    9763   19479   38867   37688
River Rch & RM= Honey Creek,Reach-1,18435
    5353    9776   14254    9985   19922   39750   38508
River Rch & RM= Honey Creek,Reach-1,14263
    6069   11128   16269   11422   22789   45470   44248
River Rch & RM= Honey Creek,Reach-1,8777
    6863   12617   18478   12990   25919   51716   50461
Boundary for River Rch & Prof#=Honey Creek,Reach-1,1
Up Type=0
Dn Type=3
Dn Slope=0.005
Boundary for River Rch & Prof#=Honey Creek,Reach-1,2
Up Type=0
Dn Type=3
Dn Slope=0.005
Boundary for River Rch & Prof#=Honey Creek,Reach-1,3
Up Type=0
Dn Type=3
Dn Slope=0.005
Boundary for River Rch & Prof#=Honey Creek,Reach-1,4
Up Type=0
Dn Type=3
Dn Slope=0.005
Boundary for River Rch & Prof#=Honey Creek,Reach-1,5
Up Type=0
Dn Type=3
Dn Slope=0.005
Boundary for River Rch & Prof#=Honey Creek,Reach-1,6
Up Type=0
Dn Type=3
Dn Slope=0.005
Boundary for River Rch & Prof#=Honey Creek,Reach-1,7
Up Type=0
Dn Type=3
Dn Slope=0.005

--- Honey Creek.g01 (geometry) ---

Geom Title=Existing Conditions

River Reach=Honey Creek,Reach-1
Reach XY= 30
      1832025.00     13954725.00      1833226.46     13955671.46
      1834519.16     13955622.95      1835691.29     13953858.29
      1837345.54     13952755.53      1838071.59     13951582.81
      1839078.41     13951917.23      1839472.55     13951280.46
      1840605.01     13951074.94      1842359.78     13951874.48
      1843580.93     13950377.24      1846375.00     13950282.56
      1847375.00     13950925.00      1849780.86     13948977.05
      1851327.29     13949619.15      1852168.95     13947683.15
      1854121.26     13947873.48      1853861.53     13947111.43
      1852725.05     13946254.99      1852936.24     13945315.00
      1853868.79     13944332.81      1855071.33     13943582.69
      1855673.72     13943778.52      1856364.25     13944215.29
      1857040.41     13945674.87      1858116.85     13944881.05
      1857858.36     13943958.32      1856315.00     13943264.37
      1856026.63     13942518.96      1856975.00     13940825.00

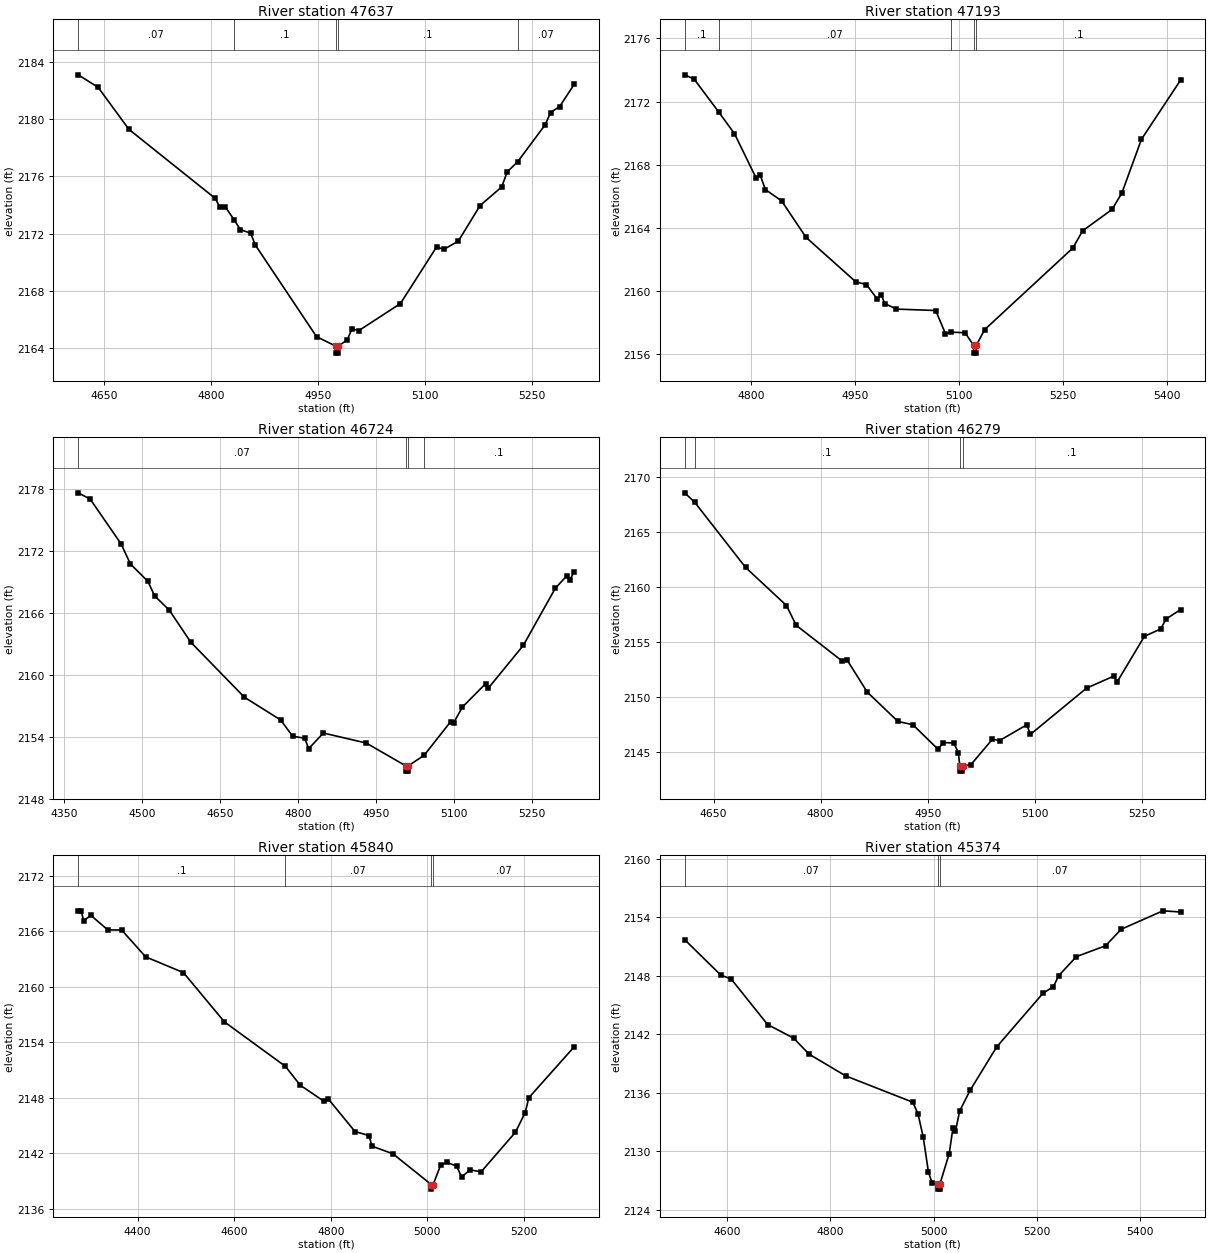
Type RM Length L Ch R = 1,47637,444,444,444
BEGIN DESCRIPTION:
Honey Creek 97.0
END DESCRIPTION:
XS GIS Cut Line= 3
      1831824.99     13955125.01      1832125.00     13954875.00
      1832175.01     13954574.96
#Sta/Elev= 30
  4614.1 2183.12  4642.1 2182.24  4685.1 2179.30  4806.1 2174.46  4812.6 2173.84
  4820.4 2173.85  4832.8 2172.94  4841.3 2172.27  4855.6 2172.03  4862.1 2171.20
  4948.0 2164.77  4974.6 2164.12  4974.9 2163.62  4978.4 2163.62  4978.6 2164.12
  4991.0 2164.55  4997.5 2165.32  5007.2 2165.20  5065.4 2167.09  5116.1 2171.06
  5126.3 2170.89  5146.6 2171.47  5177.0 2173.96  5207.4 2175.27  5215.0 2176.32
  5229.7 2177.03  5268.2 2179.62  5275.8 2180.48  5288.5 2180.90  5308.8 2182.45
#Mann=5,-1,0
  4614.1    0.07       0  4832.8     0.1       0  4974.6    0.05       0
  4978.6     0.1       0  5229.7    0.07       0
Bank Sta=4974.6,4978.6
Exp/Cntr=0.3,0.1

Type RM Length L Ch R = 1,47193,469,469,469
BEGIN DESCRIPTION:
Honey Creek 96.0
END DESCRIPTION:
XS GIS Cut Line= 3
      1832174.98     13955325.01      1832425.00     13955175.00
      1832724.98     13954875.02
#Sta/Elev= 30
  4704.3 2173.69  4717.9 2173.42  4753.5 2171.33  4776.2 2169.96  4807.3 2167.16
  4813.2 2167.34  4820.9 2166.42  4844.3 2165.70  4879.3 2163.40  4951.2 2160.58
  4966.7 2160.40  4982.3 2159.48  4988.1 2159.76  4993.0 2159.20  5010.0 2158.85
  5066.6 2158.76  5080.7 2157.29  5089.2 2157.39  5109.0 2157.35  5121.2 2156.56
  5121.4 2156.06  5124.9 2156.06  5125.2 2156.56  5137.3 2157.55  5264.6 2162.72
  5278.7 2163.81  5321.1 2165.16  5335.3 2166.20  5363.6 2169.61  5420.1 2173.36
#Mann=5,-1,0
  4704.3     0.1       0  4753.5    0.07       0  5089.2     0.1       0
  5121.2    0.05       0  5125.2     0.1       0
Bank Sta=5121.2,5125.2
Exp/Cntr=0.3,0.1

Type RM Length L Ch R = 1,46724,445,445,445
BEGIN DESCRIPTION:
Honey Creek 95.0
END DESCRIPTION:
XS GIS Cut Line= 3
      1832624.99     13955925.05      1832775.00     13955325.00
      1832924.99     13955025.02
#Sta/Elev= 30
  4377.3 2177.65  4400.5 2177.03  4459.8 2172.70  4477.8 2170.75  4511.3 2169.08
  4524.2 2167.67  4552.6 2166.28  4593.8 2163.18  4696.9 2157.85  4766.5 2155.65
  4789.7 2154.08  4812.9 2153.87  4820.6 2152.87  4848.9 2154.38  4931.4 2153.41
  5007.8 2151.19  5008.0 2150.69  5011.5 2150.69  5011.8 2151.19  5042.8 2152.23
  5093.6 2155.48  5099.2 2155.34  5116.0 2156.88  5160.7 2159.15  5166.3 2158.74
  5233.4 2162.87  5294.9 2168.40  5317.2 2169.62  5322.8 2169.18  5331.2 2170.02
#Mann=4,-1,0
  4377.3    0.07       0  5007.8    0.05       0  5011.8    0.07       0
  5042.8     0.1       0
Bank Sta=5007.8,5011.8
Exp/Cntr=0.3,0.1

Type RM Length L Ch R = 1,46279,439,439,439
BEGIN DESCRIPTION:
Honey Creek 94.0
END DESCRIPTION:
XS GIS Cut Line= 3
      1832874.98     13955875.02      1833125.00     13955575.00
      1833175.00     13955274.97
#Sta/Elev= 30
  4609.5 2168.55  4623.6 2167.69  4694.8 2161.77  4752.1 2158.31  4765.7 2156.51
  4830.2 2153.26  4836.7 2153.39  4865.3 2150.44  4908.3 2147.77  4929.1 2147.48
  4964.2 2145.26  4972.0 2145.85  4986.4 2145.82  4992.9 2144.94  4994.8 2143.76
  4995.0 2143.26  4998.5 2143.26  4998.8 2143.76  5010.2 2143.83  5040.6 2146.16
  5050.7 2146.04  5088.7 2147.47  5093.8 2146.60  5172.4 2150.80  5210.4 2151.89
  5215.5 2151.39  5253.5 2155.51  5276.3 2156.18  5283.9 2157.09  5304.2 2157.94
#Mann=4,-1,0
  4609.5    0.07       0  4623.6     0.1       0  4994.8    0.05       0
  4998.8     0.1       0
Bank Sta=4994.8,4998.8
Exp/Cntr=0.3,0.1

Type RM Length L Ch R = 1,45840,466,466,466
BEGIN DESCRIPTION:
Honey Creek 93.0
END DESCRIPTION:
XS GIS Cut Line= 3
      1833072.81     13956239.06      1833525.00     13955675.00
      1833575.00     13955374.98
#Sta/Elev= 30
  4277.1 2168.19  4282.8 2168.19  4288.7 2167.11  4303.1 2167.71  4338.3 2166.13
  4367.1 2166.12  4416.7 2163.22  4495.1 2161.51  4579.9 2156.19  4706.1 2151.39
  4736.8 2149.35  4786.4 2147.60  4794.4 2147.90  4850.4 2144.34  4879.2 2143.91
  4885.6 2142.76  4928.8 2141.94  5008.2 2138.62  5008.4 2138.12  5012.2 2138.62
  5027.9 2140.74  5040.6 2141.00  5060.9 2140.61  5071.0 2139.43  5088.7 2140.20
  5111.6 2139.99  5182.5 2144.26  5202.8 2146.39  5210.4 2148.00  5304.2 2153.49
#Mann=4,-1,0
  4277.1     0.1       0  4706.1    0.07       0  5008.2    0.05       0
  5012.2    0.07       0
Bank Sta=5008.2,5012.2
Exp/Cntr=0.3,0.1

Type RM Length L Ch R = 1,45374,500,500,500
BEGIN DESCRIPTION:
Honey Creek 92.0
END DESCRIPTION:
XS GIS Cut Line= 3
      1833933.57     13956104.81      1833975.00     13955625.00
      1833914.22     13955150.97
#Sta/Elev= 30
  4518.4 2151.72  4588.3 2148.09  4608.5 2147.68  4678.8 2143.02  4729.0 2141.63
  4759.1 2139.98  4830.0 2137.75  4959.8 2135.05  4969.9 2133.84  4979.9 2131.49
  4990.0 2127.89  4997.5 2126.72  5008.1 2126.64  5008.3 2126.14  5011.8 2126.14
  5012.1 2126.64  5030.2 2129.79  5037.3 2132.36  5042.3 2132.08  5050.4 2134.15
  5070.6 2136.27  5122.0 2140.72  5211.7 2146.23  5231.9 2146.91  5242.0 2148.03
  5276.2 2149.98  5332.7 2151.10  5362.9 2152.79  5443.6 2154.68  5477.9 2154.56
#Mann=3,-1,0
  4518.4    0.07       0  5008.1    0.05       0  5012.1    0.07       0
Bank Sta=5008.1,5012.1
Exp/Cntr=0.3,0.1

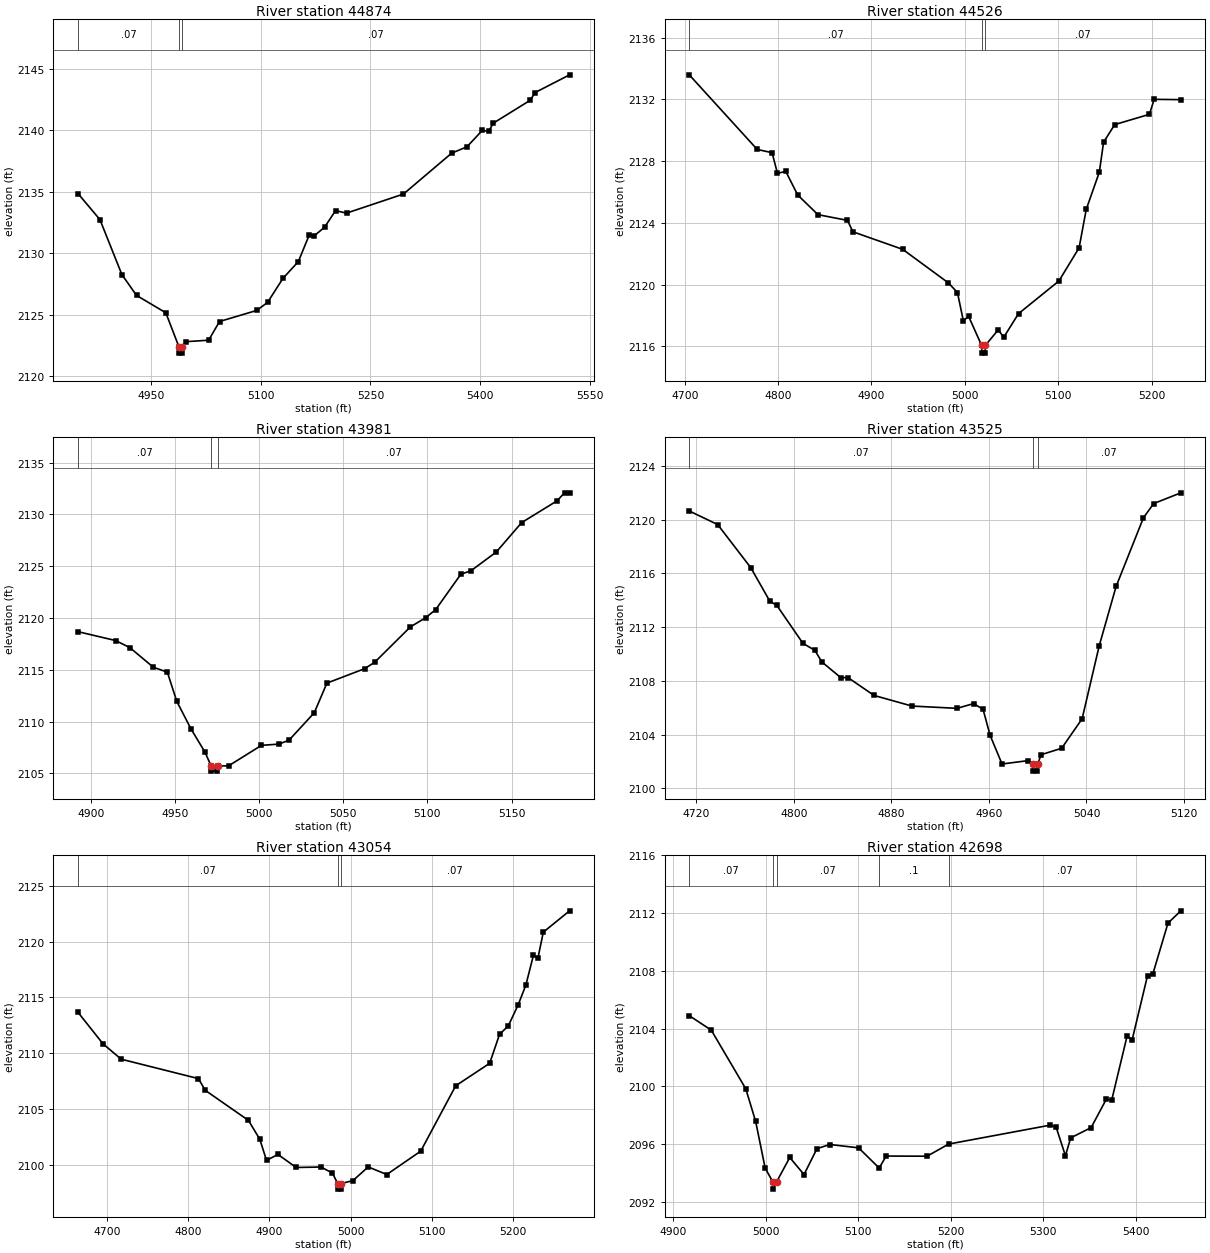
Type RM Length L Ch R = 1,44874,348,348,348
BEGIN DESCRIPTION:
Honey Creek 91.0
END DESCRIPTION:
XS GIS Cut Line= 3
      1834475.00     13955775.04      1834475.00     13955625.00
      1834181.07     13955194.03
#Sta/Elev= 30
  4850.4 2134.85  4880.4 2132.73  4910.4 2128.26  4930.4 2126.57  4970.4 2125.16
  4988.4 2122.38  4988.7 2121.88  4992.2 2121.88  4992.4 2122.38  4997.9 2122.81
  5028.9 2122.93  5043.8 2124.45  5094.6 2125.35  5109.4 2126.00  5130.5 2127.96
  5151.5 2129.32  5166.4 2131.49  5172.5 2131.38  5187.4 2132.12  5202.3 2133.46
  5217.3 2133.26  5295.1 2134.81  5360.9 2138.13  5381.9 2138.65  5402.8 2139.98
  5411.7 2139.91  5417.8 2140.57  5468.6 2142.44  5474.7 2143.05  5522.1 2144.50
#Mann=3,-1,0
  4850.4    0.07       0  4988.4    0.05       0  4992.4    0.07       0
Bank Sta=4988.4,4992.4
Exp/Cntr=0.3,0.1

Type RM Length L Ch R = 1,44526,545,545,545
BEGIN DESCRIPTION:
Honey Creek 90.0
END DESCRIPTION:
XS GIS Cut Line= 3
      1834924.98     13955524.99      1834537.82     13955305.57
      1834525.00     13955225.00
#Sta/Elev= 30
  4704.8 2133.60  4777.6 2128.76  4793.5 2128.55  4799.3 2127.21  4808.2 2127.34
  4820.9 2125.81  4842.7 2124.53  4874.3 2124.16  4880.1 2123.42  4933.5 2122.28
  4982.5 2120.10  4992.1 2119.48  4998.4 2117.65  5004.1 2117.93  5018.0 2116.05
  5018.3 2115.55  5021.8 2115.55  5022.0 2116.05  5035.9 2117.07  5041.6 2116.57
  5057.5 2118.11  5100.8 2120.23  5122.4 2122.38  5130.1 2124.88  5144.1 2127.29
  5148.6 2129.22  5160.5 2130.37  5197.8 2131.04  5202.8 2132.01  5231.4 2131.99
#Mann=3,-1,0
  4704.8    0.07       0  5018.0    0.05       0  5022.0    0.07       0
Bank Sta=5018,5022
Exp/Cntr=0.3,0.1

Type RM Length L Ch R = 1,43981,456,456,456
BEGIN DESCRIPTION:
Honey Creek 89.0
END DESCRIPTION:
XS GIS Cut Line= 3
      1834975.03     13955025.02      1834875.00     13954975.00
      1834725.01     13954875.01
#Sta/Elev= 30
  4892.4 2118.68  4914.8 2117.82  4923.2 2117.14  4937.2 2115.24  4945.5 2114.77
  4951.1 2111.95  4959.5 2109.30  4967.9 2107.03  4971.5 2105.71  4971.7 2105.21
  4975.2 2105.21  4975.5 2105.71  4981.9 2105.72  5001.4 2107.70  5011.8 2107.82
  5017.8 2108.20  5032.8 2110.85  5040.3 2113.71  5062.8 2115.11  5068.8 2115.74
  5089.9 2119.14  5098.9 2120.02  5104.9 2120.80  5119.9 2124.23  5125.9 2124.56
  5141.0 2126.38  5156.0 2129.21  5177.0 2131.31  5181.5 2132.09  5184.5 2132.09
#Mann=3,-1,0
  4892.4    0.07       0  4971.5    0.05       0  4975.5    0.07       0
Bank Sta=4971.5,4975.5
Exp/Cntr=0.3,0.1

Type RM Length L Ch R = 1,43525,471,471,471
BEGIN DESCRIPTION:
Honey Creek 88.0
END DESCRIPTION:
XS GIS Cut Line= 3
      1835275.00     13954875.00      1835125.00     13954625.00
      1835025.04     13954575.02
#Sta/Elev= 30
  4714.1 2120.64  4737.4 2119.63  4764.6 2116.42  4780.2 2113.93  4786.0 2113.61
  4807.4 2110.79  4817.1 2110.28  4822.9 2109.41  4838.5 2108.24  4844.3 2108.25
  4865.7 2106.92  4896.8 2106.13  4933.7 2105.96  4947.3 2106.31  4955.1 2105.90
  4960.9 2103.96  4970.7 2101.82  4992.0 2102.07  4995.9 2101.79  4996.1 2101.29
  4999.6 2101.29  4999.9 2101.79  5002.7 2102.51  5019.6 2102.99  5036.4 2105.18
  5050.4 2110.60  5064.3 2115.03  5086.7 2120.13  5095.1 2121.19  5117.4 2121.99
#Mann=3,-1,0
  4714.1    0.07       0  4995.9    0.05       0  4999.9    0.07       0
Bank Sta=4995.9,4999.9
Exp/Cntr=0.3,0.1

Type RM Length L Ch R = 1,43054,356,356,356
BEGIN DESCRIPTION:
Honey Creek 87.0
END DESCRIPTION:
XS GIS Cut Line= 3
      1835724.96     13954424.98      1835425.00     13954275.00
      1835175.02     13954175.01
#Sta/Elev= 30
  4664.6 2113.67  4695.3 2110.85  4717.7 2109.47  4812.7 2107.73  4821.1 2106.68
  4874.2 2103.99  4888.2 2102.30  4896.5 2100.40  4910.5 2100.94  4932.9 2099.77
  4963.6 2099.81  4977.6 2099.26  4984.0 2098.33  4984.2 2097.83  4987.7 2097.83
  4988.0 2098.33  5002.7 2098.59  5021.5 2099.82  5044.4 2099.14  5086.1 2101.23
  5129.2 2107.09  5170.9 2109.10  5183.1 2111.70  5193.8 2112.45  5205.9 2114.33
  5215.4 2116.10  5224.8 2118.79  5230.2 2118.50  5236.9 2120.85  5269.2 2122.76
#Mann=3,-1,0
  4664.6    0.07       0  4984.0    0.05       0  4988.0    0.07       0
Bank Sta=4984,4988
Exp/Cntr=0.3,0.1

Type RM Length L Ch R = 1,42698,532,532,532
BEGIN DESCRIPTION:
Honey Creek 86.0
END DESCRIPTION:
XS GIS Cut Line= 3
      1835774.95     13954074.99      1835667.75     13954049.90
      1835475.02     13953675.04
#Sta/Elev= 30
  4917.4 2104.89  4941.2 2103.89  4978.5 2099.83  4989.2 2097.57  4999.5 2094.33
  5007.8 2093.38  5008.0 2092.88  5011.8 2093.38  5026.1 2095.07  5041.5 2093.89
  5055.5 2095.68  5069.3 2095.97  5100.5 2095.74  5122.8 2094.34  5130.3 2095.17
  5174.6 2095.16  5197.9 2096.00  5307.7 2097.31  5314.1 2097.18  5324.2 2095.19
  5329.9 2096.43  5352.0 2097.14  5368.6 2099.13  5374.2 2099.03  5390.8 2103.46
  5396.4 2103.23  5413.0 2107.67  5418.6 2107.75  5435.1 2111.30  5449.0 2112.15
#Mann=5,-1,0
  4917.4    0.07       0  5007.8    0.05       0  5011.8    0.07       0
  5122.8     0.1       0  5197.9    0.07       0
Bank Sta=5007.8,5011.8
Exp/Cntr=0.3,0.1

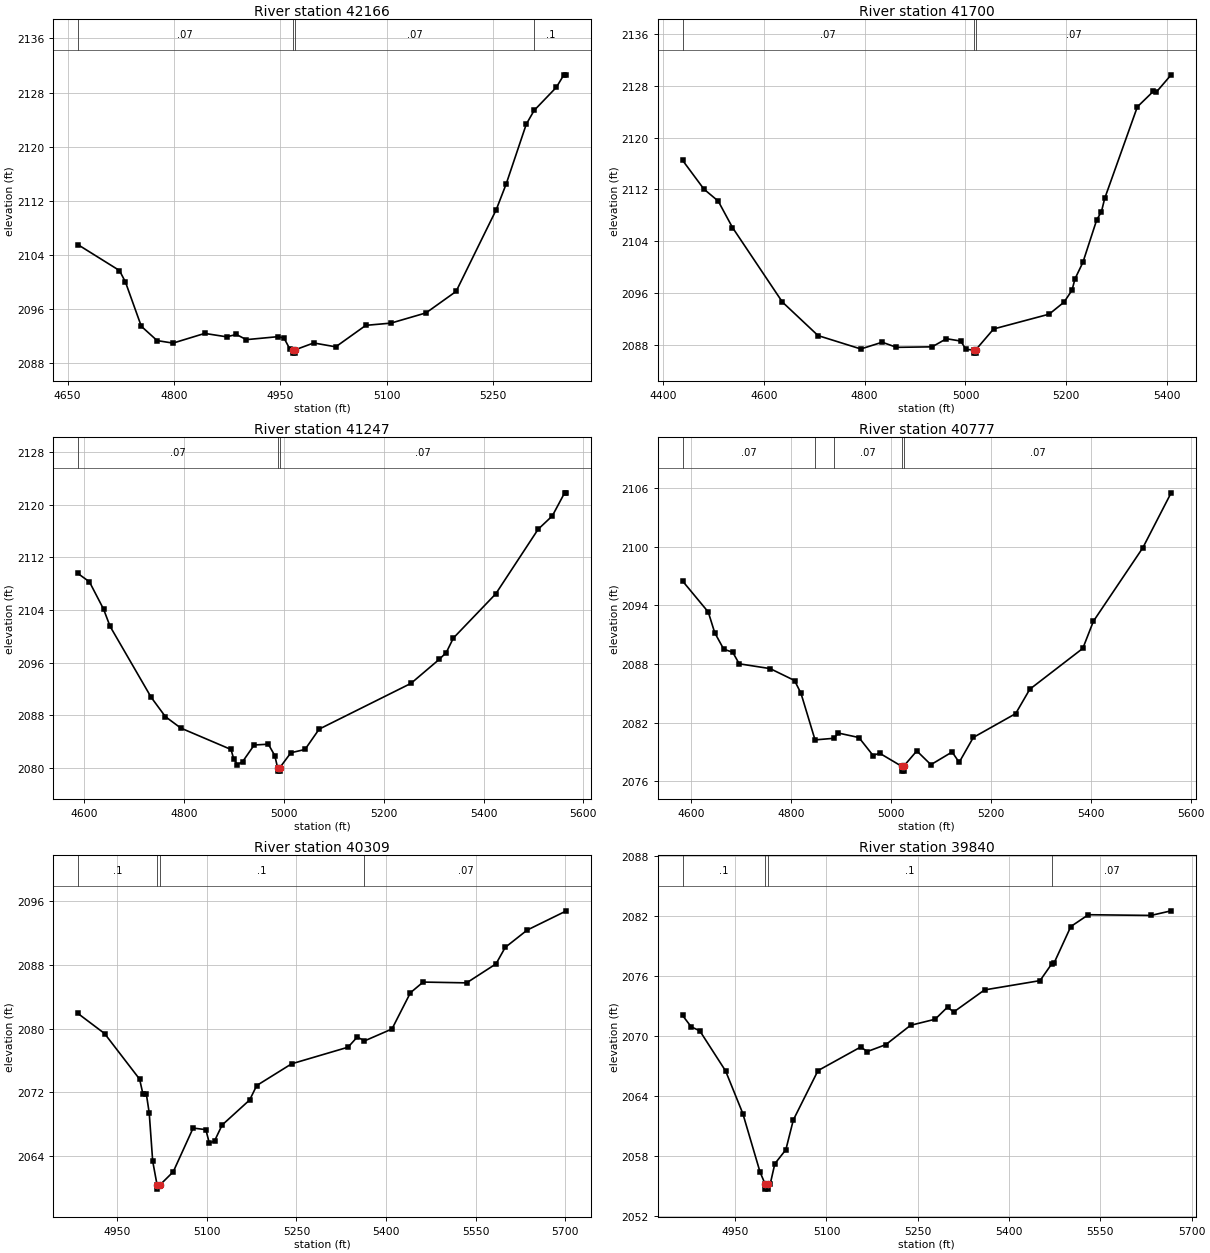
Type RM Length L Ch R = 1,42166,466,466,466
BEGIN DESCRIPTION:
Honey Creek 85.0
END DESCRIPTION:
XS GIS Cut Line= 3
      1836075.01     13953975.02      1835925.00     13953675.00
      1835674.99     13953424.99
#Sta/Elev= 30
  4664.5 2105.55  4723.2 2101.72  4731.6 2100.03  4754.0 2093.49  4776.3 2091.38
  4798.7 2091.01  4843.4 2092.44  4874.2 2091.94  4888.1 2092.28  4902.1 2091.52
  4946.8 2091.96  4955.2 2091.76  4963.6 2090.11  4967.2 2090.03  4967.4 2089.53
  4970.9 2089.53  4971.2 2090.03  4997.1 2091.03  5028.2 2090.46  5070.6 2093.63
  5106.0 2093.96  5155.5 2095.47  5197.9 2098.64  5254.5 2110.70  5268.6 2114.52
  5296.9 2123.33  5308.0 2125.36  5339.3 2128.77  5349.9 2130.61  5353.5 2130.61
#Mann=4,-1,0
  4664.5    0.07       0  4967.2    0.05       0  4971.2    0.07       0
  5308.0     0.1       0
Bank Sta=4967.2,4971.2
Exp/Cntr=0.3,0.1

Type RM Length L Ch R = 1,41700,453,453,453
BEGIN DESCRIPTION:
Honey Creek 84.0
END DESCRIPTION:
XS GIS Cut Line= 3
      1836674.98     13953824.98      1836275.00     13953425.00
      1835924.97     13953224.98
#Sta/Elev= 30
  4439.0 2116.49  4481.4 2112.05  4509.7 2110.21  4538.0 2106.14  4637.0 2094.66
  4707.7 2089.50  4792.5 2087.44  4834.9 2088.48  4863.2 2087.69  4933.9 2087.77
  4962.2 2089.02  4990.5 2088.66  5001.1 2087.36  5016.3 2087.30  5016.6 2086.80
  5020.1 2086.80  5020.3 2087.30  5055.8 2090.52  5165.9 2092.80  5195.4 2094.65
  5211.3 2096.49  5217.0 2098.21  5232.8 2100.77  5260.2 2107.31  5269.6 2108.58
  5276.0 2110.61  5340.8 2124.72  5372.5 2127.11  5378.3 2126.98  5407.8 2129.65
#Mann=3,-1,0
  4439.0    0.07       0  5016.3    0.05       0  5020.3    0.07       0
Bank Sta=5016.3,5020.3
Exp/Cntr=0.3,0.1

Type RM Length L Ch R = 1,41247,470,470,470
BEGIN DESCRIPTION:
Honey Creek 83.0
END DESCRIPTION:
XS GIS Cut Line= 3
      1836774.99     13953674.96      1836675.00     13953275.00
      1836274.97     13952874.97
#Sta/Elev= 30
  4588.0 2109.56  4611.1 2108.30  4639.5 2104.14  4652.4 2101.54  4734.8 2090.74
  4763.2 2087.81  4794.1 2086.07  4894.6 2082.82  4899.8 2081.43  4907.5 2080.51
  4917.8 2080.97  4941.0 2083.50  4969.3 2083.62  4982.2 2081.89  4987.9 2080.03
  4988.2 2079.53  4991.8 2079.53  4992.0 2080.03  5014.4 2082.32  5042.7 2082.82
  5071.0 2085.91  5254.8 2092.86  5311.4 2096.51  5325.5 2097.55  5339.7 2099.75
  5424.5 2106.46  5509.4 2116.28  5537.7 2118.30  5562.4 2121.81  5566.0 2121.81
#Mann=3,-1,0
  4588.0    0.07       0  4987.9    0.05       0  4992.0    0.07       0
Bank Sta=4987.9,4992
Exp/Cntr=0.3,0.1

Type RM Length L Ch R = 1,40777,468,468,468
BEGIN DESCRIPTION:
Honey Creek 82.0
END DESCRIPTION:
XS GIS Cut Line= 3
      1837124.99     13953374.98      1837025.00     13952975.00
      1836624.98     13952574.98
#Sta/Elev= 30
  4582.9 2096.50  4634.4 2093.32  4647.3 2091.20  4665.3 2089.52  4683.4 2089.20
  4696.3 2088.02  4758.1 2087.53  4807.1 2086.31  4820.0 2084.99  4848.1 2080.23
  4885.5 2080.39  4894.7 2080.93  4935.9 2080.47  4964.3 2078.63  4977.2 2078.87
  5021.4 2077.53  5021.7 2077.03  5025.3 2077.03  5025.5 2077.53  5051.8 2079.10
  5080.0 2077.69  5122.5 2078.99  5136.6 2077.93  5164.9 2080.48  5249.7 2082.92
  5278.0 2085.42  5384.1 2089.60  5405.3 2092.38  5504.3 2099.91  5560.9 2105.53
#Mann=5,-1,0
  4582.9    0.07       0  4848.1     0.1       0  4885.5    0.07       0
  5021.4    0.05       0  5025.5    0.07       0
Bank Sta=5021.4,5025.5
Exp/Cntr=0.3,0.1

Type RM Length L Ch R = 1,40309,469,469,469
BEGIN DESCRIPTION:
Honey Creek 81.0
END DESCRIPTION:
XS GIS Cut Line= 3
      1837474.96     13952774.98      1837375.00     13952725.00
      1836772.46     13952356.61
#Sta/Elev= 30
  4884.0 2081.91  4928.7 2079.38  4987.4 2073.64  4993.0 2071.76  4998.7 2071.76
  5003.5 2069.39  5009.3 2063.33  5016.7 2060.31  5017.0 2059.81  5021.1 2060.31
  5043.7 2061.99  5077.0 2067.49  5098.3 2067.29  5104.2 2065.57  5113.0 2065.89
  5125.5 2067.87  5171.6 2071.02  5183.5 2072.84  5241.9 2075.57  5336.4 2077.66
  5351.8 2078.94  5363.9 2078.45  5409.9 2079.95  5440.8 2084.51  5462.1 2085.85
  5534.9 2085.75  5584.1 2088.14  5599.5 2090.21  5636.3 2092.39  5702.0 2094.81
#Mann=4,-1,0
  4884.0     0.1       0  5016.7    0.05       0  5021.1     0.1       0
  5363.9    0.07       0
Bank Sta=5016.7,5021.1
Exp/Cntr=0.3,0.1

Type RM Length L Ch R = 1,39840,592,592,592
BEGIN DESCRIPTION:
Honey Creek 80.0
END DESCRIPTION:
XS GIS Cut Line= 3
      1837675.02     13952425.02      1837575.00     13952325.00
      1836922.36     13952218.68
#Sta/Elev= 30
  4863.6 2072.10  4877.8 2070.96  4891.9 2070.56  4934.3 2066.55  4962.6 2062.29
  4990.9 2056.44  4999.3 2055.23  4999.6 2054.73  5003.4 2054.73  5003.7 2055.23
  5007.6 2055.23  5015.2 2057.27  5033.3 2058.67  5045.6 2061.65  5086.1 2066.58
  5156.2 2068.94  5167.2 2068.49  5197.6 2069.18  5238.1 2071.11  5278.6 2071.72
  5298.9 2072.93  5309.0 2072.44  5359.7 2074.65  5450.9 2075.58  5470.4 2077.28
  5473.8 2077.32  5501.5 2080.99  5530.3 2082.17  5633.2 2082.10  5666.3 2082.56
#Mann=4,-1,0
  4863.6     0.1       0  4999.3    0.05       0  5003.7     0.1       0
  5470.4    0.07       0
Bank Sta=4999.3,5003.7
Exp/Cntr=0.3,0.1

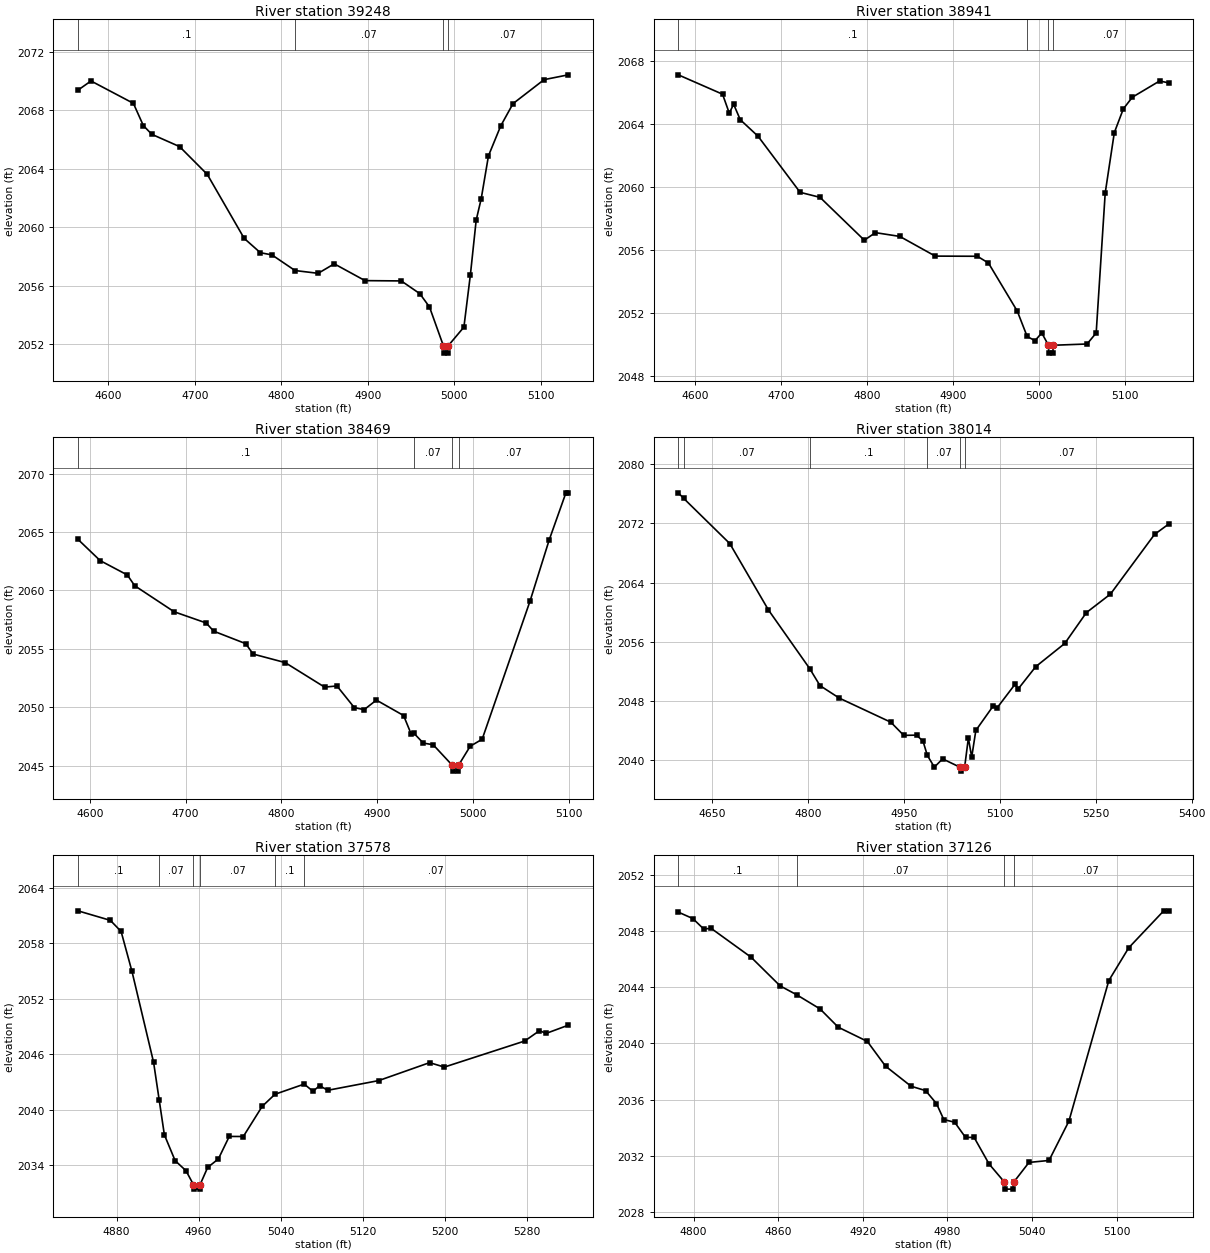
Type RM Length L Ch R = 1,39248,307,307,307
BEGIN DESCRIPTION:
Honey Creek 79.0
END DESCRIPTION:
XS GIS Cut Line= 3
      1837874.99     13952224.98      1837732.24     13951844.46
      1837625.03     13951725.04
#Sta/Elev= 30
  4565.0 2069.39  4580.1 2070.02  4629.1 2068.49  4640.6 2066.97  4650.4 2066.37
  4682.5 2065.53  4714.5 2063.63  4757.2 2059.25  4775.9 2058.27  4789.3 2058.12
  4816.0 2057.05  4842.7 2056.86  4861.3 2057.51  4896.9 2056.36  4938.8 2056.34
  4960.2 2055.47  4971.4 2054.56  4987.5 2051.90  4988.0 2051.40  4992.6 2051.40
  4993.0 2051.90  5011.2 2053.18  5018.7 2056.76  5025.4 2060.50  5031.2 2061.96
  5039.6 2064.90  5053.8 2066.95  5068.0 2068.47  5103.9 2070.11  5131.9 2070.44
#Mann=4,-1,0
  4565.0     0.1       0  4816.0    0.07       0  4987.5    0.05       0
  4993.0    0.07       0
Bank Sta=4987.5,4993
Exp/Cntr=0.3,0.1

Type RM Length L Ch R = 1,38941,472,472,472
BEGIN DESCRIPTION:
Honey Creek 78.0
END DESCRIPTION:
XS GIS Cut Line= 3
      1838075.00     13952074.98      1837975.00     13951675.00
      1837825.01     13951625.00
#Sta/Elev= 30
  4580.3 2067.11  4631.8 2065.88  4639.6 2064.68  4644.7 2065.24  4652.4 2064.26
  4673.1 2063.21  4722.0 2059.65  4745.2 2059.33  4796.7 2056.61  4809.6 2057.09
  4838.0 2056.85  4879.2 2055.60  4928.2 2055.59  4941.1 2055.16  4974.6 2052.11
  4986.1 2050.50  4995.2 2050.23  5003.1 2050.72  5010.9 2049.94  5011.3 2049.44
  5016.0 2049.44  5016.5 2049.94  5055.8 2050.02  5066.4 2050.72  5076.9 2059.61
  5087.5 2063.44  5098.0 2064.95  5108.5 2065.69  5140.2 2066.72  5150.7 2066.60
#Mann=4,-1,0
  4580.3     0.1       0  4986.1    0.07       0  5010.9    0.05       0
  5016.5    0.07       0
Bank Sta=5010.9,5016.5
Exp/Cntr=0.3,0.1

Type RM Length L Ch R = 1,38469,455,455,455
BEGIN DESCRIPTION:
Honey Creek 77.0
END DESCRIPTION:
XS GIS Cut Line= 3
      1838274.99     13951975.04      1838375.00     13951575.00
      1838375.00     13951475.05
#Sta/Elev= 30
  4587.5 2064.37  4610.7 2062.55  4639.1 2061.32  4646.8 2060.40  4688.0 2058.17
  4721.5 2057.21  4729.3 2056.51  4762.8 2055.44  4770.5 2054.55  4804.0 2053.82
  4845.2 2051.72  4858.1 2051.82  4876.2 2049.97  4886.5 2049.79  4899.3 2050.61
  4927.7 2049.29  4935.4 2047.75  4938.5 2047.77  4948.3 2046.93  4958.6 2046.79
  4978.6 2045.03  4979.1 2044.53  4984.6 2044.53  4985.1 2045.03  4997.3 2046.66
  5009.8 2047.26  5059.8 2059.08  5079.8 2064.31  5097.3 2068.35  5099.8 2068.35
#Mann=4,-1,0
  4587.5     0.1       0  4938.5    0.07       0  4978.6    0.05       0
  4985.1    0.07       0
Bank Sta=4978.6,4985.1
Exp/Cntr=0.3,0.1

Type RM Length L Ch R = 1,38014,436,436,436
BEGIN DESCRIPTION:
Honey Creek 76.0
END DESCRIPTION:
XS GIS Cut Line= 3
      1838725.00     13952124.97      1838775.00     13951725.00
      1838675.00     13951374.99
#Sta/Elev= 30
  4596.9 2076.14  4605.1 2075.41  4677.5 2069.27  4738.0 2060.28  4802.5 2052.35
  4818.6 2050.05  4848.8 2048.36  4929.4 2045.10  4949.6 2043.32  4969.7 2043.35
  4979.8 2042.52  4986.5 2040.61  4997.5 2039.02  5010.4 2040.14  5038.3 2038.98
  5038.8 2038.48  5044.8 2038.98  5050.7 2042.96  5055.9 2040.37  5062.4 2043.99
  5089.7 2047.32  5094.9 2046.96  5123.5 2050.21  5128.7 2049.61  5156.0 2052.61
  5201.5 2055.76  5235.3 2059.93  5273.0 2062.44  5341.9 2070.51  5364.0 2071.91
#Mann=6,-1,0
  4596.9     0.1       0  4605.1    0.07       0  4802.5     0.1       0
  4986.5    0.07       0  5038.3    0.05       0  5044.8    0.07       0
Bank Sta=5038.3,5044.8
Exp/Cntr=0.3,0.1

Type RM Length L Ch R = 1,37578,452,452,452
BEGIN DESCRIPTION:
Honey Creek 75.0
END DESCRIPTION:
XS GIS Cut Line= 3
      1839274.98     13951924.99      1839125.00     13951875.00
      1838924.97     13951624.96
#Sta/Elev= 30
  4842.3 2061.53  4873.9 2060.50  4884.4 2059.30  4895.0 2054.98  4916.1 2045.14
  4921.6 2041.04  4926.6 2037.31  4937.1 2034.51  4947.7 2033.42  4954.9 2031.93
  4955.4 2031.43  4961.0 2031.43  4961.5 2031.93  4968.8 2033.77  4979.3 2034.70
  4989.9 2037.13  5003.6 2037.12  5022.0 2040.38  5034.5 2041.69  5063.0 2042.79
  5071.6 2042.01  5078.0 2042.62  5086.0 2042.12  5135.7 2043.17  5185.3 2045.11
  5199.7 2044.63  5278.1 2047.45  5292.5 2048.57  5298.9 2048.27  5320.6 2049.16
#Mann=6,-1,0
  4842.3     0.1       0  4921.6    0.07       0  4954.9    0.05       0
  4961.5    0.07       0  5034.5     0.1       0  5063.0    0.07       0
Bank Sta=4954.9,4961.5
Exp/Cntr=0.3,0.1

Type RM Length L Ch R = 1,37126,455,455,455
BEGIN DESCRIPTION:
Honey Creek 74.0
END DESCRIPTION:
XS GIS Cut Line= 3
      1839375.01     13951725.03      1839325.00     13951525.00
      1839225.01     13951425.01
#Sta/Elev= 30
  4789.2 2049.34  4799.5 2048.88  4807.3 2048.13  4812.4 2048.19  4840.8 2046.13
  4861.4 2044.09  4873.1 2043.46  4889.7 2042.45  4902.6 2041.15  4923.2 2040.14
  4936.1 2038.38  4954.2 2036.95  4964.5 2036.64  4972.2 2035.72  4977.4 2034.58
  4985.1 2034.39  4992.8 2033.31  4998.9 2033.31  5009.5 2031.42  5020.4 2030.13
  5020.9 2029.63  5026.5 2029.63  5027.0 2030.13  5037.8 2031.53  5052.0 2031.67
  5066.1 2034.47  5094.4 2044.47  5108.5 2046.80  5133.3 2049.43  5136.8 2049.43
#Mann=4,-1,0
  4789.2     0.1       0  4873.1    0.07       0  5020.4    0.05       0
  5027.0    0.07       0
Bank Sta=5020.4,5027
Exp/Cntr=0.3,0.1

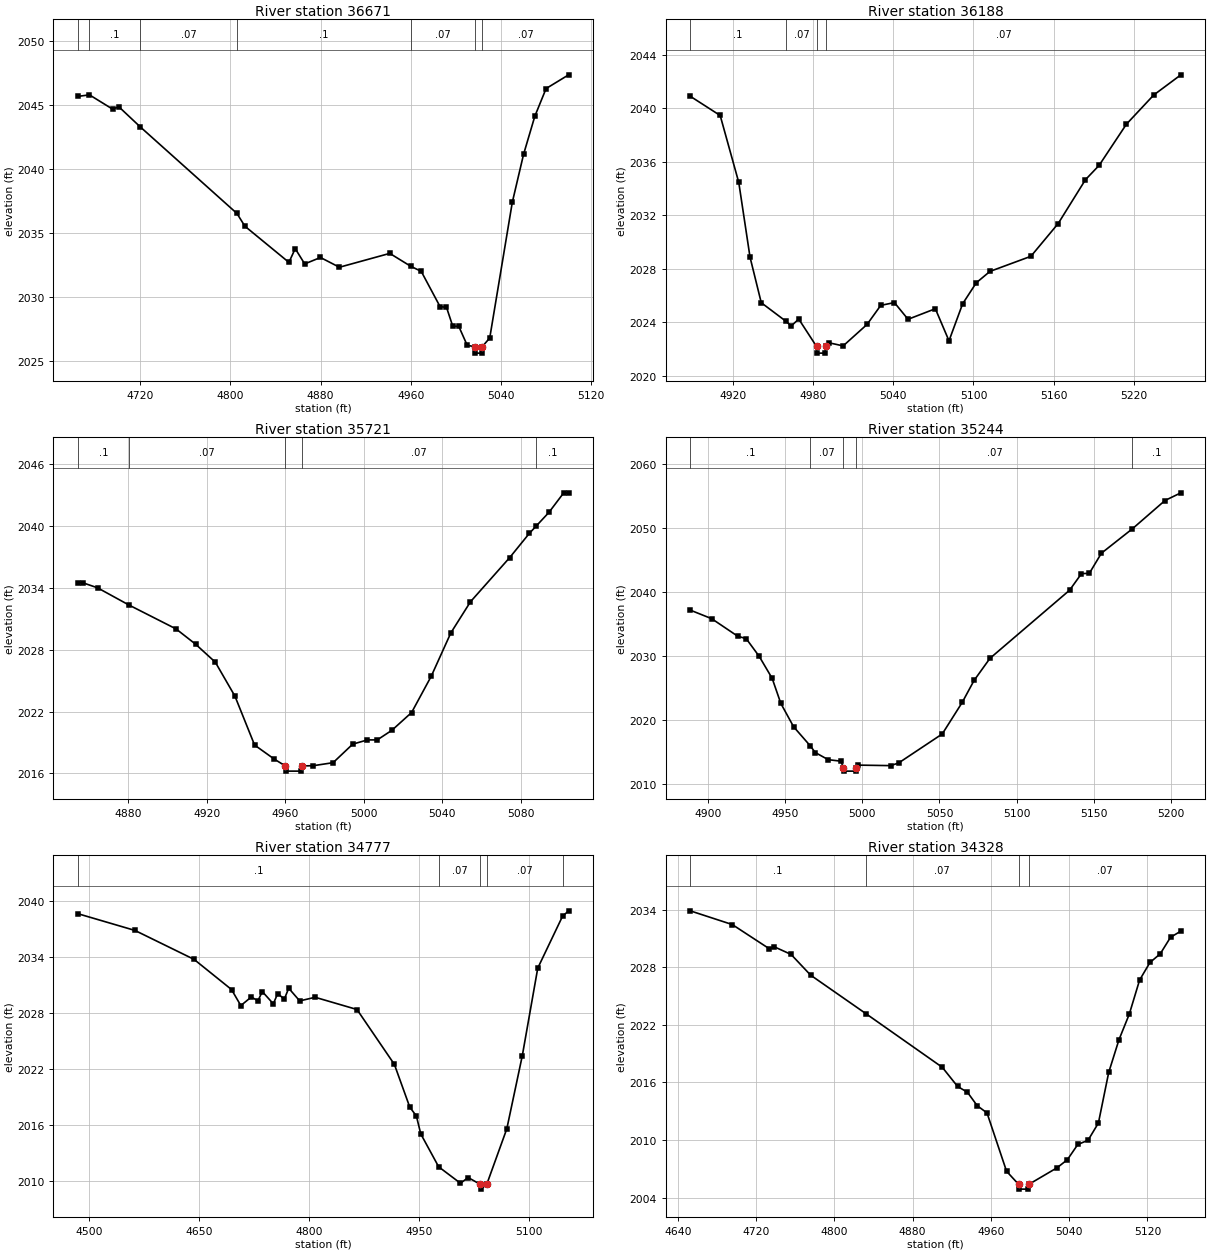
Type RM Length L Ch R = 1,36671,483,483,483
BEGIN DESCRIPTION:
Honey Creek 73.0
END DESCRIPTION:
XS GIS Cut Line= 3
      1839774.99     13951574.98      1839625.00     13951275.00
      1839625.00     13951174.98
#Sta/Elev= 30
  4664.7 2045.65  4674.9 2045.77  4695.4 2044.66  4701.0 2044.84  4719.8 2043.29
  4805.8 2036.53  4812.8 2035.54  4851.9 2032.72  4857.5 2033.79  4865.9 2032.60
  4879.9 2033.10  4896.7 2032.34  4941.4 2033.42  4960.1 2032.41  4969.3 2032.02
  4986.1 2029.26  4991.7 2029.23  4997.3 2027.74  5002.6 2027.74  5010.1 2026.26
  5016.7 2026.15  5017.2 2025.65  5022.9 2025.65  5023.4 2026.15  5030.1 2026.83
  5050.1 2037.39  5060.1 2041.13  5070.1 2044.10  5080.1 2046.26  5100.1 2047.33
#Mann=7,-1,0
  4664.7    0.07       0  4674.9     0.1       0  4719.8    0.07       0
  4805.8     0.1       0  4960.1    0.07       0  5016.7    0.05       0
  5023.4    0.07       0
Bank Sta=5016.7,5023.4
Exp/Cntr=0.3,0.1

Type RM Length L Ch R = 1,36188,467,467,467
BEGIN DESCRIPTION:
Honey Creek 72.0
END DESCRIPTION:
XS GIS Cut Line= 3
      1840125.00     13951374.99      1840075.00     13951275.00
      1840124.99     13951025.05
#Sta/Elev= 30
  4888.3 2040.91  4910.7 2039.47  4924.6 2034.46  4933.0 2028.88  4941.4 2025.47
  4960.0 2024.07  4963.8 2023.73  4969.4 2024.25  4982.7 2022.20  4983.2 2021.70
  4989.1 2021.70  4989.6 2022.20  4991.7 2022.48  5002.6 2022.24  5020.5 2023.85
  5030.7 2025.27  5040.9 2025.48  5051.1 2024.23  5071.5 2025.02  5081.7 2022.62
  5091.9 2025.39  5102.1 2026.96  5112.3 2027.81  5142.9 2028.94  5163.3 2031.39
  5183.7 2034.67  5193.9 2035.74  5214.3 2038.82  5234.7 2041.00  5255.0 2042.51
#Mann=4,-1,0
  4888.3     0.1       0  4960.0    0.07       0  4982.7    0.05       0
  4989.6    0.07       0
Bank Sta=4982.7,4989.6
Exp/Cntr=0.3,0.1

Type RM Length L Ch R = 1,35721,477,477,477
BEGIN DESCRIPTION:
Honey Creek 71.0
END DESCRIPTION:
XS GIS Cut Line= 3
      1840475.00     13951224.96      1840475.00     13951075.00
      1840475.00     13950974.96
#Sta/Elev= 30
  4854.3 2034.50  4856.8 2034.50  4864.3 2034.01  4880.2 2032.35  4904.3 2030.02
  4914.3 2028.53  4924.3 2026.79  4934.3 2023.49  4944.3 2018.75  4954.3 2017.39
  4960.0 2016.72  4960.5 2016.22  4968.0 2016.22  4968.5 2016.72  4974.3 2016.75
  4984.3 2017.04  4994.3 2018.84  5001.8 2019.25  5006.8 2019.25  5014.3 2020.19
  5024.3 2021.91  5034.3 2025.43  5044.3 2029.64  5054.3 2032.66  5074.3 2036.95
  5084.3 2039.30  5087.8 2040.01  5094.3 2041.34  5101.8 2043.23  5104.3 2043.23
#Mann=5,-1,0
  4854.3     0.1       0  4880.2    0.07       0  4960.0    0.05       0
  4968.5    0.07       0  5087.8     0.1       0
Bank Sta=4960,4968.5
Exp/Cntr=0.3,0.1

Type RM Length L Ch R = 1,35244,467,467,467
BEGIN DESCRIPTION:
Honey Creek 70.0
END DESCRIPTION:
XS GIS Cut Line= 3
      1840825.02     13951374.96      1840875.00     13951275.00
      1840925.00     13951075.01
#Sta/Elev= 30
  4888.5 2037.22  4902.4 2035.88  4919.2 2033.15  4924.8 2032.75  4933.2 2029.99
  4941.6 2026.55  4947.2 2022.64  4955.5 2018.98  4966.4 2015.97  4969.5 2014.96
  4977.9 2013.84  4986.3 2013.60  4987.6 2012.55  4988.1 2012.05  4995.6 2012.05
  4996.1 2012.55  4997.5 2012.99  5018.3 2012.91  5023.5 2013.32  5051.8 2017.86
  5064.7 2022.78  5072.4 2026.22  5082.7 2029.68  5134.3 2040.33  5142.0 2042.92
  5147.1 2042.97  5154.9 2046.11  5175.0 2049.93  5196.1 2054.35  5206.4 2055.55
#Mann=5,-1,0
  4888.5     0.1       0  4966.4    0.07       0  4987.6    0.05       0
  4996.1    0.07       0  5175.0     0.1       0
Bank Sta=4987.6,4996.1
Exp/Cntr=0.3,0.1

Type RM Length L Ch R = 1,34777,449,449,449
BEGIN DESCRIPTION:
Honey Creek 69.0
END DESCRIPTION:
XS GIS Cut Line= 3
      1840850.49     13951759.50      1841275.00     13951475.00
      1841324.99     13951325.04
#Sta/Elev= 30
  4484.8 2038.68  4562.5 2036.89  4643.1 2033.79  4694.2 2030.56  4706.9 2028.84
  4721.2 2029.76  4730.2 2029.35  4736.2 2030.34  4751.2 2029.03  4757.2 2030.13
  4766.2 2029.53  4772.2 2030.70  4787.2 2029.34  4808.2 2029.73  4865.3 2028.42
  4916.3 2022.54  4937.3 2017.96  4946.3 2017.01  4952.3 2015.09  4976.7 2011.57
  5006.4 2009.81  5016.9 2010.42  5033.7 2009.68  5034.2 2009.18  5042.2 2009.68
  5069.6 2015.64  5090.7 2023.46  5111.8 2032.85  5145.6 2038.41  5153.9 2038.99
#Mann=5,-1,0
  4484.8     0.1       0  4976.7    0.07       0  5033.7    0.05       0
  5042.2    0.07       0  5145.6     0.1       0
Bank Sta=5033.7,5042.2
Exp/Cntr=0.3,0.1

Type RM Length L Ch R = 1,34328,481,481,481
BEGIN DESCRIPTION:
Honey Creek 68.0
END DESCRIPTION:
XS GIS Cut Line= 3
      1841644.86     13952067.89      1841625.00     13951725.00
      1841675.01     13951574.98
#Sta/Elev= 30
  4652.6 2033.88  4695.6 2032.45  4733.6 2029.92  4738.6 2030.13  4755.7 2029.34
  4775.7 2027.18  4832.2 2023.17  4910.3 2017.58  4925.9 2015.59  4936.0 2014.98
  4946.0 2013.58  4956.0 2012.83  4976.0 2006.75  4988.3 2005.39  4988.8 2004.89
  4998.3 2004.89  4998.8 2005.39  5027.7 2007.12  5038.2 2007.96  5048.8 2009.54
  5059.3 2009.98  5069.9 2011.78  5080.4 2017.04  5090.9 2020.45  5101.5 2023.13
  5112.0 2026.67  5122.6 2028.50  5133.1 2029.40  5143.6 2031.12  5154.2 2031.77
#Mann=4,-1,0
  4652.6     0.1       0  4832.2    0.07       0  4988.3    0.05       0
  4998.8    0.07       0
Bank Sta=4988.3,4998.8
Exp/Cntr=0.3,0.1