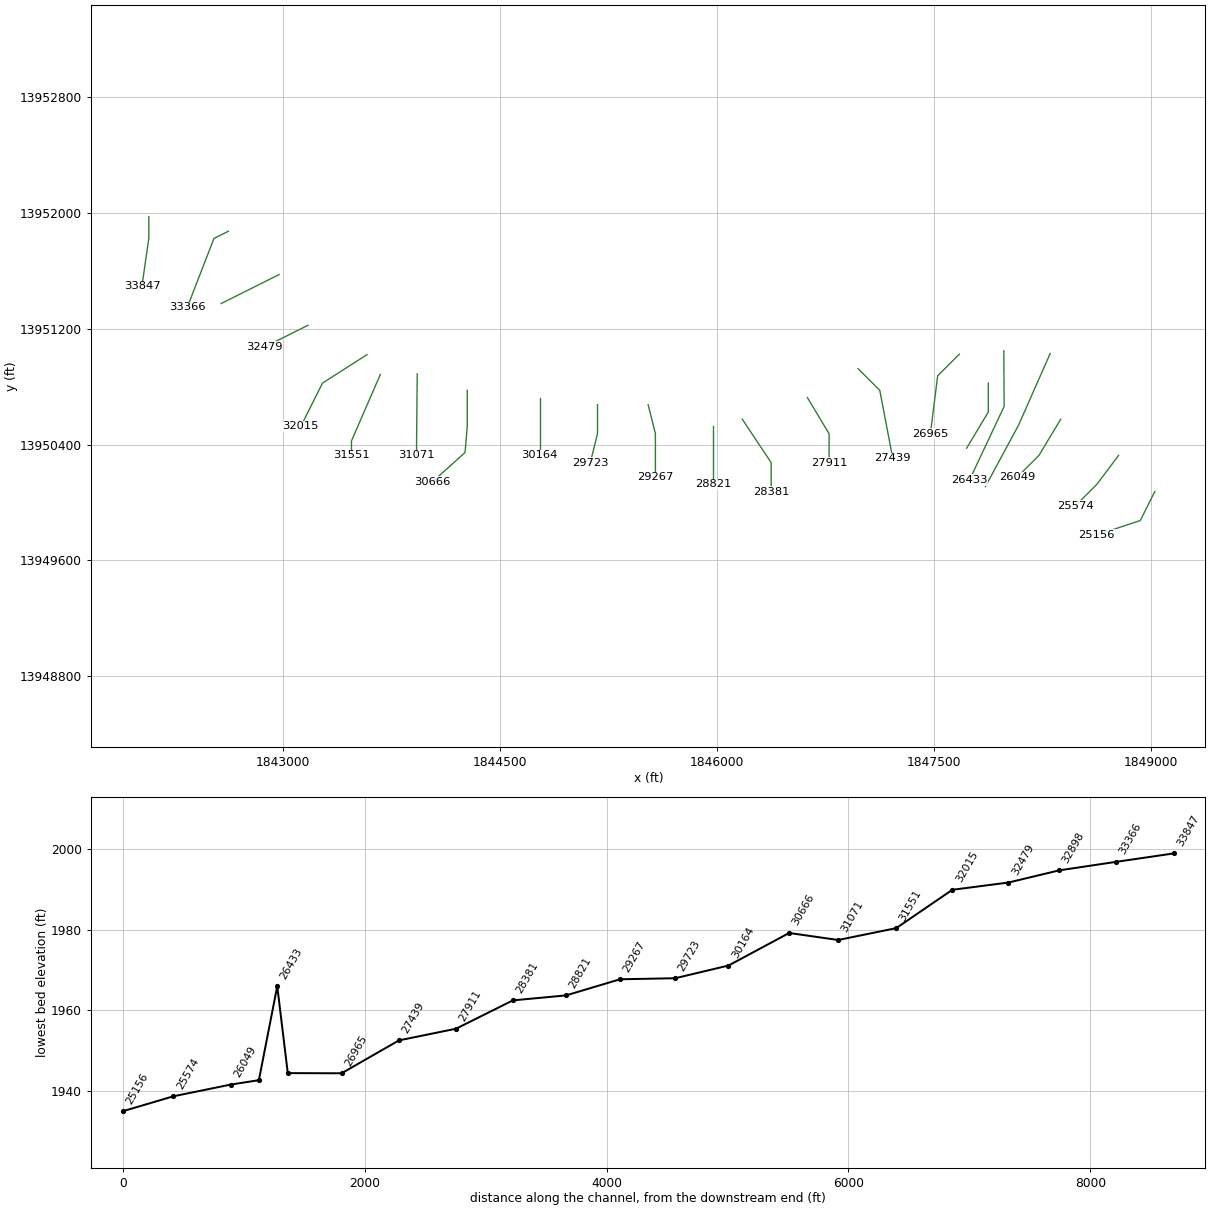
HEC-RAS study Honey Creek.prj: Honey Creek Base Level Engineering

--- Honey Creek.g01 (geometry) --- (continued)

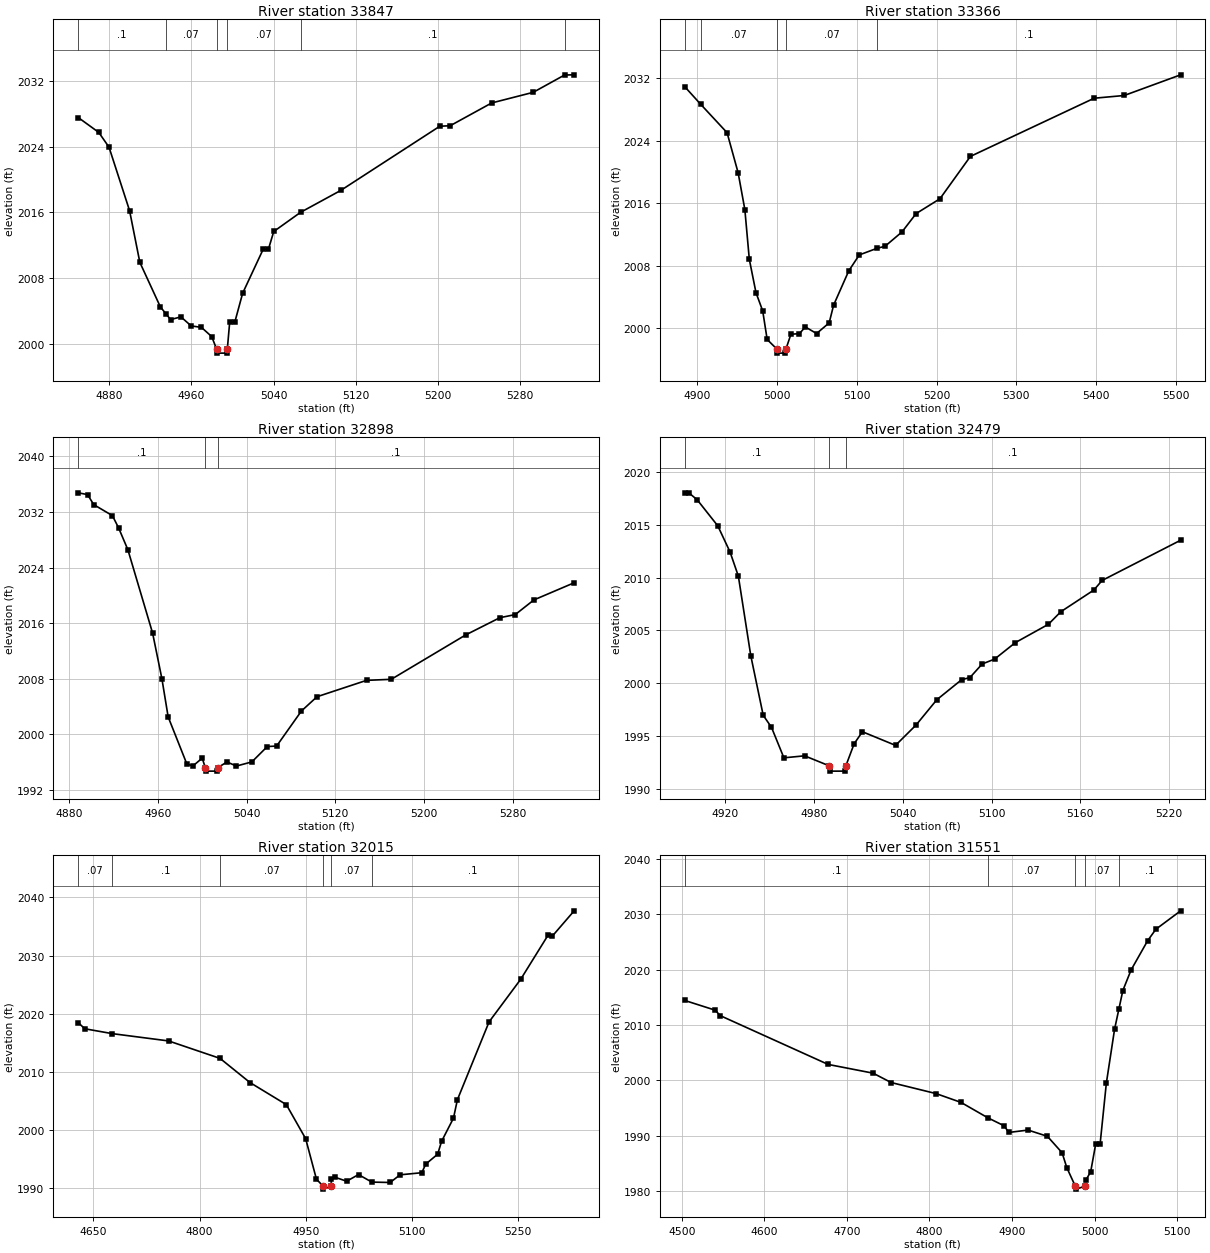
Type RM Length L Ch R = 1,33847,481,481,481
BEGIN DESCRIPTION:
Honey Creek 67.0
END DESCRIPTION:
XS GIS Cut Line= 3
      1842075.00     13951974.99      1842075.00     13951825.00
      1842027.48     13951495.50
#Sta/Elev= 30
  4849.7 2027.55  4869.7 2025.74  4879.7 2023.94  4899.7 2016.23  4909.7 2009.94
  4929.7 2004.52  4935.2 2003.67  4939.7 2002.98  4949.7 2003.31  4959.7 2002.21
  4969.7 2002.03  4979.7 2000.91  4984.4 1999.40  4984.9 1998.90  4994.4 1998.90
  4994.9 1999.40  4997.2 2002.68  5002.2 2002.68  5009.8 2006.18  5029.8 2011.53
  5034.9 2011.53  5040.1 2013.69  5066.2 2016.02  5105.3 2018.68  5201.8 2026.49
  5211.9 2026.55  5252.3 2029.32  5292.7 2030.61  5323.3 2032.72  5332.6 2032.74
#Mann=6,-1,0
  4849.7     0.1       0  4935.2    0.07       0  4984.4    0.05       0
  4994.9    0.07       0  5066.2     0.1       0  5323.3    0.07       0
Bank Sta=4984.4,4994.9
Exp/Cntr=0.3,0.1

Type RM Length L Ch R = 1,33366,468,468,468
BEGIN DESCRIPTION:
Honey Creek 66.0
END DESCRIPTION:
XS GIS Cut Line= 3
      1842625.04     13951875.02      1842525.00     13951825.00
      1842340.74     13951348.97
#Sta/Elev= 30
  4884.0 2030.96  4904.2 2028.68  4937.2 2025.05  4951.1 2019.90  4959.5 2015.20
  4965.1 2008.82  4973.5 2004.53  4981.9 2002.21  4987.5 1998.54  4999.9 1997.29
  5000.4 1996.79  5010.5 1996.79  5011.0 1997.29  5017.3 1999.21  5028.0 1999.29
  5035.4 2000.15  5049.5 1999.30  5065.3 2000.67  5070.9 2002.95  5089.9 2007.34
  5103.1 2009.38  5125.9 2010.25  5135.3 2010.48  5156.7 2012.33  5174.4 2014.68
  5204.3 2016.58  5242.5 2022.01  5397.8 2029.47  5435.5 2029.82  5506.3 2032.47
#Mann=5,-1,0
  4884.0     0.1       0  4904.2    0.07       0  4999.9    0.05       0
  5011.0    0.07       0  5125.9     0.1       0
Bank Sta=4999.9,5011
Exp/Cntr=0.3,0.1

Type RM Length L Ch R = 1,32898,419,419,419
BEGIN DESCRIPTION:
Honey Creek 65.0
END DESCRIPTION:
XS GIS Cut Line= 3
      1842975.03     13951575.01      1842875.00     13951525.00
      1842575.04     13951375.02
#Sta/Elev= 30
  4888.2 2034.76  4896.6 2034.51  4902.2 2033.06  4919.0 2031.48  4924.6 2029.72
  4933.0 2026.56  4955.3 2014.55  4963.7 2007.96  4969.3 2002.50  4986.1 1995.74
  4991.6 1995.43  5000.0 1996.56  5002.8 1995.19  5003.3 1994.69  5013.5 1994.69
  5014.0 1995.19  5022.4 1996.01  5030.8 1995.42  5044.8 1996.02  5058.7 1998.23
  5067.1 1998.30  5089.5 2003.35  5103.5 2005.40  5148.2 2007.76  5170.5 2007.91
  5237.6 2014.30  5268.4 2016.78  5282.3 2017.23  5299.1 2019.34  5335.4 2021.81
#Mann=3,-1,0
  4888.2     0.1       0  5002.8    0.05       0  5014.0     0.1       0
Bank Sta=5002.8,5014
Exp/Cntr=0.3,0.1

Type RM Length L Ch R = 1,32479,464,464,464
BEGIN DESCRIPTION:
Honey Creek 64.0
END DESCRIPTION:
XS GIS Cut Line= 3
      1843175.00     13951225.00      1843075.00     13951175.00
      1842875.01     13951075.01
#Sta/Elev= 30
  4892.5 2018.03  4895.3 2018.03  4900.9 2017.38  4914.9 2014.90  4923.2 2012.42
  4928.8 2010.14  4937.2 2002.61  4945.6 1996.96  4951.2 1995.82  4959.6 1992.93
  4973.6 1993.12  4990.3 1992.17  4990.8 1991.67  5001.0 1991.67  5001.5 1992.17
  5007.1 1994.26  5012.7 1995.40  5035.1 1994.11  5049.0 1996.04  5063.0 1998.43
  5079.8 2000.33  5085.4 2000.53  5093.7 2001.82  5102.1 2002.28  5116.1 2003.84
  5138.5 2005.58  5146.9 2006.77  5169.2 2008.82  5174.8 2009.73  5227.9 2013.54
#Mann=3,-1,0
  4892.5     0.1       0  4990.3    0.05       0  5001.5     0.1       0
Bank Sta=4990.3,5001.5
Exp/Cntr=0.3,0.1

Type RM Length L Ch R = 1,32015,464,464,464
BEGIN DESCRIPTION:
Honey Creek 63.0
END DESCRIPTION:
XS GIS Cut Line= 3
      1843582.79     13951021.82      1843275.00     13950825.00
      1843124.98     13950524.96
#Sta/Elev= 30
  4628.6 2018.49  4637.9 2017.43  4676.9 2016.59  4756.3 2015.34  4829.0 2012.34
  4871.3 2008.19  4922.7 2004.39  4950.0 1998.54  4965.2 1991.59  4974.7 1990.37
  4975.2 1989.87  4986.0 1990.37  4986.3 1991.53  4991.0 1991.93  5007.9 1991.23
  5024.7 1992.37  5043.5 1991.08  5069.4 1991.01  5083.4 1992.33  5114.1 1992.69
  5119.7 1994.17  5136.5 1995.87  5142.1 1998.09  5158.9 2002.08  5164.4 2005.23
  5209.2 2018.62  5253.9 2025.94  5293.0 2033.61  5298.6 2033.36  5329.4 2037.70
#Mann=6,-1,0
  4628.6    0.07       0  4676.9     0.1       0  4829.0    0.07       0
  4974.7    0.05       0  4986.0    0.07       0  5043.5     0.1       0
Bank Sta=4974.7,4986
Exp/Cntr=0.3,0.1

Type RM Length L Ch R = 1,31551,480,480,480
BEGIN DESCRIPTION:
Honey Creek 62.0
END DESCRIPTION:
XS GIS Cut Line= 3
      1843674.54     13950884.40      1843475.00     13950425.00
      1843475.00     13950324.97
#Sta/Elev= 30
  4503.4 2014.44  4540.4 2012.68  4546.4 2011.70  4677.2 2002.88  4731.7 2001.30
  4753.5 1999.61  4808.0 1997.61  4838.2 1996.02  4870.8 1993.23  4890.6 1991.78
  4896.0 1990.59  4919.5 1991.02  4942.9 1989.89  4960.7 1986.92  4966.4 1984.23
  4976.8 1980.85  4977.3 1980.35  4988.2 1980.85  4989.8 1982.07  4995.3 1983.46
  5001.5 1988.58  5006.8 1988.58  5014.3 1999.49  5024.3 2009.26  5029.6 2012.95
  5034.3 2016.23  5044.3 2019.95  5064.3 2025.22  5074.3 2027.30  5104.3 2030.63
#Mann=5,-1,0
  4503.4     0.1       0  4870.8    0.07       0  4976.8    0.05       0
  4988.2    0.07       0  5029.6     0.1       0
Bank Sta=4976.8,4988.2
Exp/Cntr=0.3,0.1

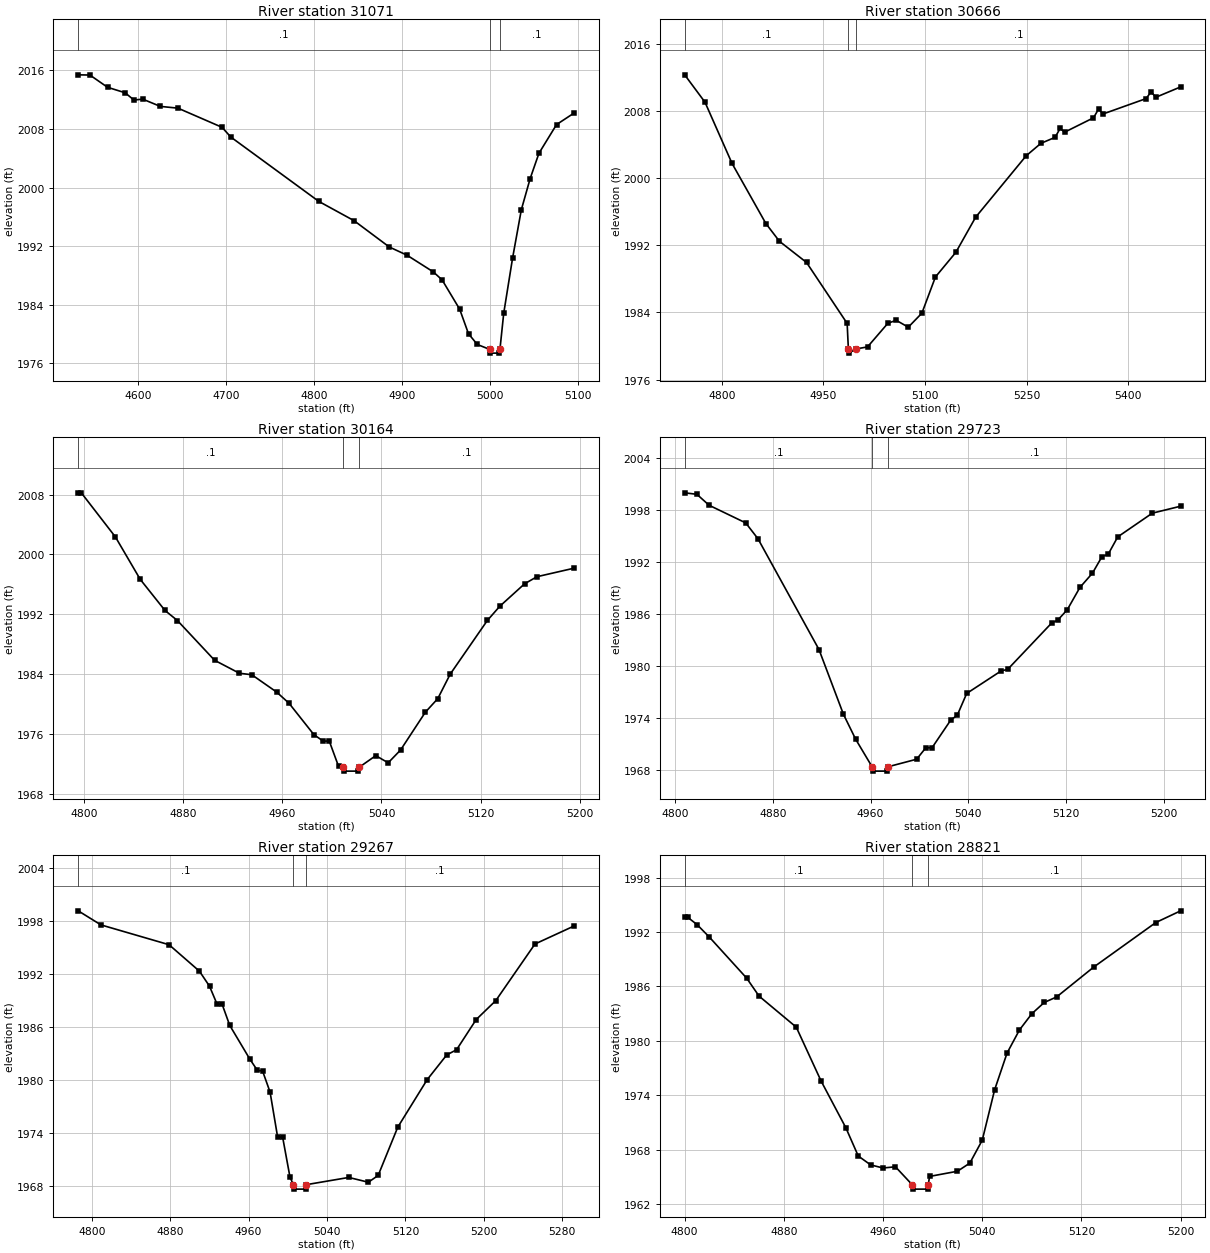
Type RM Length L Ch R = 1,31071,405,405,405
BEGIN DESCRIPTION:
Honey Creek 61.0
END DESCRIPTION:
XS GIS Cut Line= 3
      1843929.44     13950888.32      1843925.00     13950425.00
      1843925.00     13950325.04
#Sta/Elev= 30
  4532.0 2015.40  4545.3 2015.37  4565.3 2013.70  4585.3 2012.95  4595.3 2011.96
  4605.3 2012.08  4625.3 2011.09  4645.3 2010.85  4695.3 2008.24  4705.3 2006.91
  4805.3 1998.12  4845.3 1995.49  4885.3 1991.90  4905.3 1990.79  4935.3 1988.50
  4945.3 1987.41  4965.3 1983.40  4975.3 1980.05  4985.3 1978.59  4999.6 1977.91
  5000.1 1977.41  5010.5 1977.41  5011.0 1977.91  5015.3 1982.85  5025.3 1990.34
  5035.3 1996.98  5045.3 2001.23  5055.3 2004.69  5075.3 2008.61  5095.3 2010.19
#Mann=3,-1,0
  4532.0     0.1       0  4999.6    0.05       0  5011.0     0.1       0
Bank Sta=4999.6,5011
Exp/Cntr=0.3,0.1

Type RM Length L Ch R = 1,30666,502,502,502
BEGIN DESCRIPTION:
Honey Creek 60.0
END DESCRIPTION:
XS GIS Cut Line= 4
      1844275.00     13950775.02      1844275.00     13950525.00
      1844259.88     13950345.20      1844035.48     13950142.88
#Sta/Elev= 30
  4745.0 2012.30  4775.0 2009.04  4815.0 2001.74  4865.0 1994.58  4885.0 1992.47
  4925.0 1989.95  4985.0 1982.69  4986.8 1979.65  4987.3 1979.15  4998.2 1979.65
  5015.1 1979.89  5045.2 1982.71  5057.5 1983.06  5075.3 1982.24  5095.4 1983.91
  5115.4 1988.22  5145.6 1991.16  5174.8 1995.34  5249.5 2002.66  5271.2 2004.14
  5292.1 2004.85  5299.6 2005.91  5306.3 2005.47  5348.9 2007.18  5356.4 2008.22
  5363.1 2007.64  5426.6 2009.47  5434.1 2010.29  5440.8 2009.62  5477.6 2010.86
#Mann=3,-1,0
  4745.0     0.1       0  4986.8    0.05       0  4998.2     0.1       0
Bank Sta=4986.8,4998.2
Exp/Cntr=0.3,0.1

Type RM Length L Ch R = 1,30164,441,441,441
BEGIN DESCRIPTION:
Honey Creek 59.0
END DESCRIPTION:
XS GIS Cut Line= 3
      1844775.00     13950725.03      1844775.00     13950525.00
      1844775.00     13950325.03
#Sta/Elev= 30
  4795.4 2008.23  4797.9 2008.23  4825.4 2002.34  4845.4 1996.68  4865.4 1992.52
  4875.4 1991.18  4905.4 1985.87  4925.4 1984.14  4935.4 1983.94  4955.4 1981.63
  4965.4 1980.14  4985.4 1975.96  4992.9 1975.08  4997.9 1975.08  5005.4 1971.70
  5009.0 1971.57  5009.5 1971.07  5021.4 1971.07  5021.9 1971.57  5035.4 1973.14
  5045.4 1972.18  5055.4 1973.89  5075.4 1978.94  5085.4 1980.75  5095.4 1984.01
  5125.4 1991.19  5135.4 1993.08  5155.4 1996.08  5165.4 1997.03  5195.4 1998.17
#Mann=3,-1,0
  4795.4     0.1       0  5009.0    0.05       0  5021.9     0.1       0
Bank Sta=5009,5021.9
Exp/Cntr=0.3,0.1

Type RM Length L Ch R = 1,29723,456,456,456
BEGIN DESCRIPTION:
Honey Creek 58.0
END DESCRIPTION:
XS GIS Cut Line= 3
      1845175.00     13950675.04      1845175.00     13950475.00
      1845125.00     13950274.99
#Sta/Elev= 30
  4807.8 1999.94  4817.8 1999.77  4827.8 1998.51  4857.8 1996.48  4867.8 1994.66
  4917.8 1981.91  4937.8 1974.47  4947.8 1971.60  4961.3 1968.42  4961.8 1967.92
  4973.8 1967.92  4974.3 1968.42  4997.8 1969.29  5005.3 1970.61  5010.4 1970.61
  5025.9 1973.83  5031.0 1974.33  5038.8 1976.86  5067.1 1979.46  5072.3 1979.62
  5108.3 1984.95  5113.5 1985.31  5121.2 1986.50  5131.5 1989.05  5141.8 1990.70
  5149.6 1992.60  5154.7 1992.88  5162.5 1994.87  5190.8 1997.60  5214.0 1998.40
#Mann=3,-1,0
  4807.8     0.1       0  4961.3    0.05       0  4974.3     0.1       0
Bank Sta=4961.3,4974.3
Exp/Cntr=0.3,0.1

Type RM Length L Ch R = 1,29267,446,446,446
BEGIN DESCRIPTION:
Honey Creek 57.0
END DESCRIPTION:
XS GIS Cut Line= 3
      1845525.01     13950674.97      1845575.00     13950475.00
      1845575.00     13950175.02
#Sta/Elev= 30
  4786.1 1999.11  4809.3 1997.52  4878.8 1995.28  4909.8 1992.29  4920.1 1990.59
  4927.8 1988.56  4933.0 1988.54  4940.7 1986.17  4961.3 1982.34  4969.0 1981.07
  4974.2 1981.02  4981.9 1978.62  4989.6 1973.54  4994.7 1973.54  5002.2 1969.02
  5005.7 1968.16  5006.2 1967.66  5018.2 1967.66  5018.7 1968.16  5062.2 1968.98
  5082.2 1968.44  5092.2 1969.21  5112.2 1974.66  5142.2 1980.03  5162.2 1982.83
  5172.2 1983.41  5192.2 1986.82  5212.2 1988.96  5252.2 1995.36  5292.2 1997.40
#Mann=3,-1,0
  4786.1     0.1       0  5005.7    0.05       0  5018.7     0.1       0
Bank Sta=5005.7,5018.7
Exp/Cntr=0.3,0.1

Type RM Length L Ch R = 1,28821,440,440,440
BEGIN DESCRIPTION:
Honey Creek 56.0
END DESCRIPTION:
XS GIS Cut Line= 3
      1845975.00     13950525.00      1845975.00     13950325.00
      1845975.00     13950125.00
#Sta/Elev= 30
  4800.0 1993.61  4802.5 1993.61  4810.0 1992.81  4820.0 1991.42  4850.0 1986.91
  4860.0 1984.93  4890.0 1981.51  4910.0 1975.58  4930.0 1970.42  4940.0 1967.31
  4950.0 1966.33  4960.0 1965.99  4970.0 1966.12  4983.4 1964.16  4983.9 1963.66
  4996.0 1963.66  4996.5 1964.16  4997.5 1965.06  5020.0 1965.63  5030.0 1966.53
  5040.0 1969.05  5050.0 1974.61  5060.0 1978.65  5070.0 1981.20  5080.0 1982.99
  5090.0 1984.23  5100.0 1984.84  5130.0 1988.14  5180.0 1993.04  5200.0 1994.33
#Mann=3,-1,0
  4800.0     0.1       0  4983.4    0.05       0  4996.5     0.1       0
Bank Sta=4983.4,4996.5
Exp/Cntr=0.3,0.1

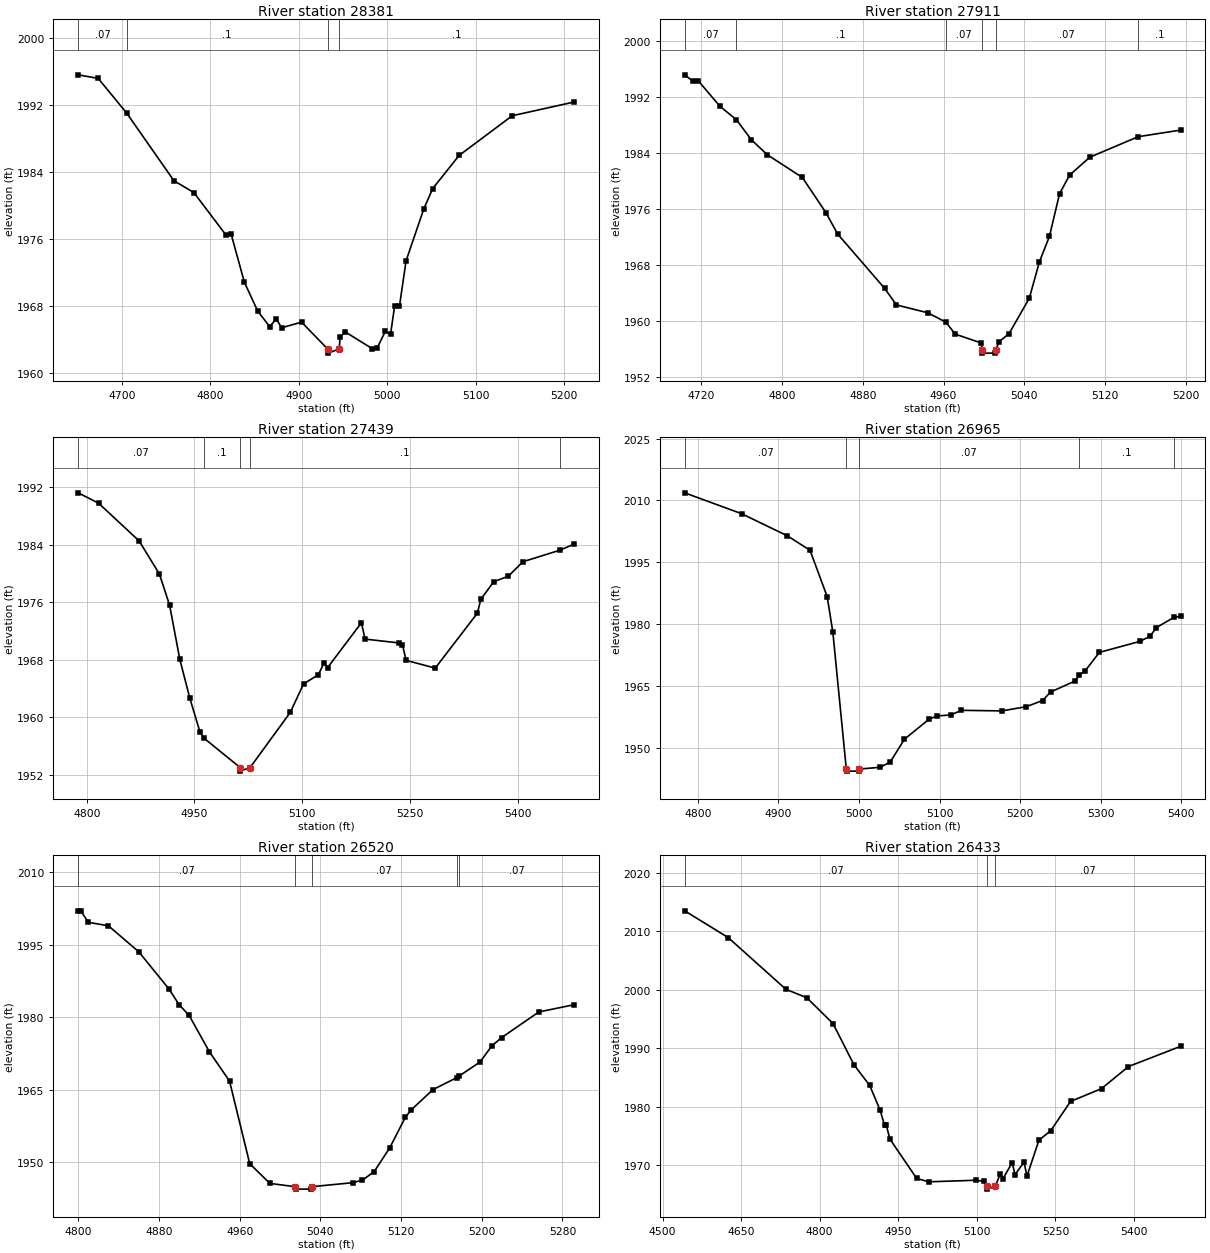
Type RM Length L Ch R = 1,28381,470,470,470
BEGIN DESCRIPTION:
Honey Creek 55.0
END DESCRIPTION:
XS GIS Cut Line= 3
      1846174.98     13950575.04      1846375.00     13950275.00
      1846375.00     13950075.00
#Sta/Elev= 30
  4650.6 1995.61  4673.2 1995.18  4705.3 1991.06  4758.8 1982.98  4781.3 1981.57
  4817.4 1976.54  4823.4 1976.64  4838.4 1970.88  4853.5 1967.44  4867.0 1965.58
  4874.5 1966.50  4880.5 1965.44  4903.0 1966.12  4932.5 1962.92  4933.0 1962.42
  4945.7 1962.92  4946.6 1964.35  4952.6 1964.94  4982.7 1962.97  4988.7 1963.08
  4997.7 1965.00  5003.7 1964.70  5008.2 1967.99  5013.7 1967.99  5021.2 1973.43
  5041.2 1979.60  5051.2 1982.03  5081.2 1986.00  5141.2 1990.73  5211.2 1992.37
#Mann=4,-1,0
  4650.6    0.07       0  4705.3     0.1       0  4932.5    0.05       0
  4945.7     0.1       0
Bank Sta=4932.5,4945.7
Exp/Cntr=0.3,0.1

Type RM Length L Ch R = 1,27911,472,472,472
BEGIN DESCRIPTION:
Honey Creek 54.0
END DESCRIPTION:
XS GIS Cut Line= 3
      1846624.99     13950725.02      1846775.00     13950475.00
      1846775.00     13950274.97
#Sta/Elev= 30
  4703.4 1995.12  4711.2 1994.25  4717.0 1994.25  4738.4 1990.62  4754.7 1988.71
  4769.5 1985.85  4785.1 1983.73  4820.0 1980.47  4843.4 1975.45  4855.0 1972.40
  4901.7 1964.62  4913.3 1962.27  4944.4 1961.15  4962.3 1959.81  4971.6 1958.10
  4997.5 1956.83  4998.1 1955.89  4998.6 1955.39  5011.4 1955.39  5011.9 1955.89
  5015.0 1957.00  5025.0 1958.19  5045.0 1963.22  5055.0 1968.41  5065.0 1972.07
  5075.0 1978.15  5085.0 1980.81  5105.0 1983.36  5153.0 1986.29  5195.0 1987.23
#Mann=6,-1,0
  4703.4    0.07       0  4754.7     0.1       0  4962.3    0.07       0
  4998.1    0.05       0  5011.9    0.07       0  5153.0     0.1       0
Bank Sta=4998.1,5011.9
Exp/Cntr=0.3,0.1

Type RM Length L Ch R = 1,27439,474,474,474
BEGIN DESCRIPTION:
Honey Creek 53.0
END DESCRIPTION:
XS GIS Cut Line= 3
      1846975.01     13950924.99      1847125.00     13950775.00
      1847214.85     13950304.93
#Sta/Elev= 30
  4788.1 1991.23  4816.4 1989.79  4872.9 1984.54  4901.2 1979.92  4915.4 1975.58
  4929.5 1968.09  4943.6 1962.62  4957.8 1957.90  4963.2 1957.08  5013.6 1952.99
  5014.1 1952.49  5027.5 1952.99  5083.4 1960.66  5102.0 1964.64  5122.4 1965.89
  5130.4 1967.53  5135.5 1966.91  5182.5 1973.14  5187.6 1970.87  5234.4 1970.34
  5239.7 1970.07  5244.8 1967.91  5285.3 1966.83  5343.9 1974.46  5348.9 1976.42
  5366.7 1978.85  5387.1 1979.62  5407.5 1981.64  5459.1 1983.25  5478.8 1984.10
#Mann=5,-1,0
  4788.1    0.07       0  4963.2     0.1       0  5013.6    0.05       0
  5027.5     0.1       0  5459.1    0.07       0
Bank Sta=5013.6,5027.5
Exp/Cntr=0.3,0.1

Type RM Length L Ch R = 1,26965,445,445,445
BEGIN DESCRIPTION:
Honey Creek 52.0
END DESCRIPTION:
XS GIS Cut Line= 3
      1847674.98     13951024.98      1847525.00     13950875.00
      1847475.00     13950475.02
#Sta/Elev= 30
  4783.8 2011.84  4854.5 2006.77  4911.1 2001.42  4939.3 1997.90  4960.6 1986.64
  4967.6 1978.04  4984.3 1944.83  4984.8 1944.33  4999.9 1944.33  5000.4 1944.83
  5026.1 1945.26  5038.7 1946.51  5056.4 1952.07  5086.6 1956.87  5096.7 1957.71
  5114.3 1957.97  5126.9 1959.08  5177.3 1958.94  5207.5 1959.96  5227.7 1961.46
  5237.8 1963.53  5268.0 1966.19  5273.2 1967.58  5280.6 1968.67  5298.2 1973.13
  5348.6 1975.81  5361.2 1977.06  5368.8 1979.14  5390.8 1981.63  5399.0 1981.88
#Mann=5,-1,0
  4783.8    0.07       0  4984.3    0.05       0  5000.4    0.07       0
  5273.2     0.1       0  5390.8    0.07       0
Bank Sta=4984.3,5000.4
Exp/Cntr=0.3,0.1

Type RM Length L Ch R = 1,26520,87,87,87
BEGIN DESCRIPTION:
Honey Creek 51.0
END DESCRIPTION:
XS GIS Cut Line= 3
      1847875.00     13950825.02      1847875.00     13950625.00
      1847724.98     13950374.97
#Sta/Elev= 30
  4800.0 2002.00  4802.5 2002.00  4810.0 1999.63  4830.0 1998.89  4860.0 1993.52
  4890.0 1985.81  4900.0 1982.57  4910.0 1980.33  4930.0 1972.82  4950.0 1966.75
  4970.0 1949.64  4990.0 1945.55  5015.3 1944.87  5015.8 1944.37  5030.9 1944.37
  5031.4 1944.87  5071.9 1945.70  5081.7 1946.23  5093.3 1947.98  5108.9 1952.95
  5124.4 1959.30  5130.2 1960.80  5151.6 1964.97  5175.3 1967.46  5177.2 1967.74
  5198.3 1970.69  5209.9 1974.01  5219.6 1975.73  5256.6 1981.06  5291.6 1982.56
#Mann=5,-1,0
  4800.0    0.07       0  5015.3    0.05       0  5031.4    0.07       0
  5175.3     0.1       0  5177.2    0.07       0
Bank Sta=5015.3,5031.4
Exp/Cntr=0.3,0.1

Type RM Length L Ch R = 1,26433,152,152,152
BEGIN DESCRIPTION:
Honey Creek 50.2
END DESCRIPTION:
XS GIS Cut Line= 3
      1847982.24     13951048.21      1847984.21     13950663.30
      1847744.95     13950154.91
#Sta/Elev= 30
  4542.3 2013.50  4625.5 2008.92  4735.5 2000.09  4775.5 1998.64  4825.5 1994.23
  4865.5 1987.18  4895.5 1983.66  4915.5 1979.40  4923.9 1976.86  4927.2 1976.86
  4934.0 1974.50  4985.1 1967.77  5007.9 1967.18  5099.1 1967.45  5113.2 1967.25
  5119.3 1966.43  5119.8 1965.93  5135.4 1966.43  5144.7 1968.52  5150.2 1967.74
  5167.5 1970.47  5173.0 1968.41  5190.2 1970.54  5195.8 1968.16  5218.6 1974.29
  5241.4 1975.95  5279.0 1980.92  5338.1 1983.11  5389.5 1986.88  5489.1 1990.34
#Mann=3,-1,0
  4542.3    0.07       0  5119.3    0.05       0  5135.4    0.07       0
Bank Sta=5119.3,5135.4
Exp/Cntr=0.3,0.1

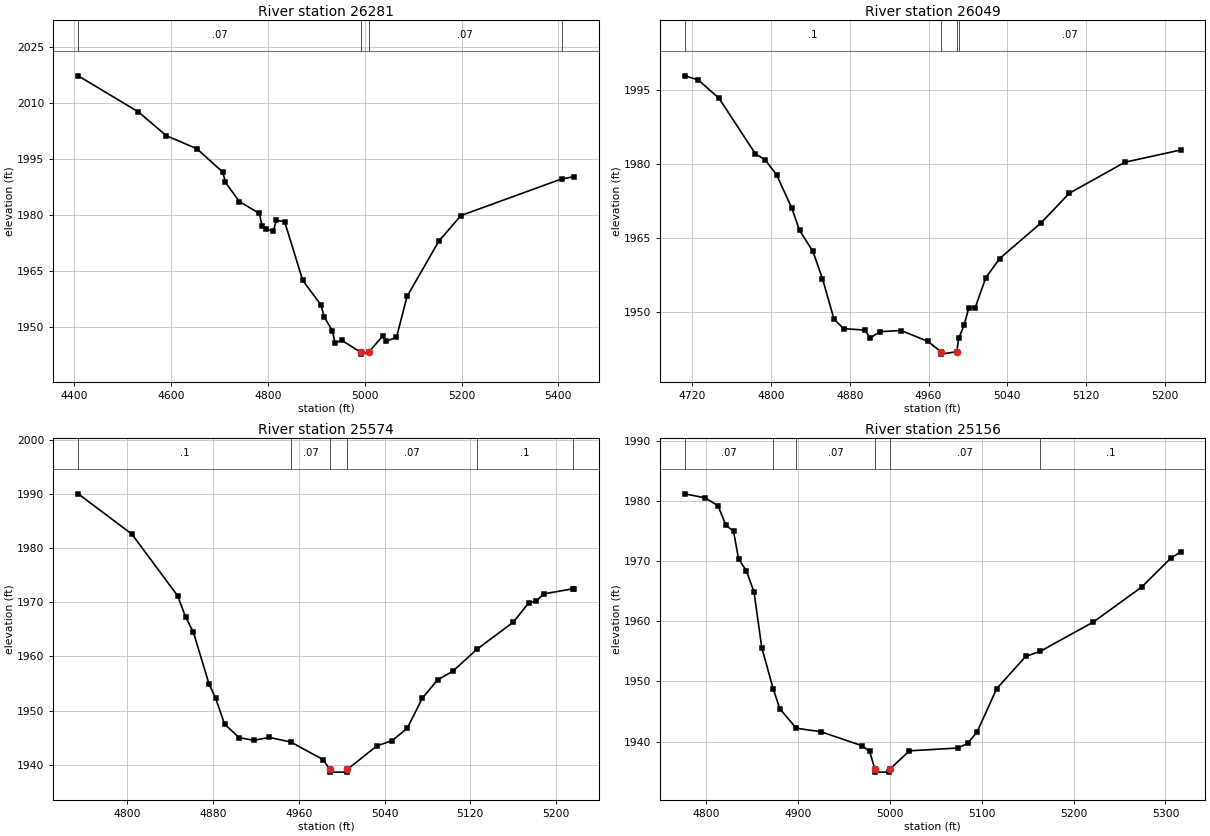
Type RM Length L Ch R = 1,26281,232,232,232
BEGIN DESCRIPTION:
Honey Creek 50.1
END DESCRIPTION:
XS GIS Cut Line= 3
      1848302.28     13951029.10      1848083.72     13950533.76
      1847854.77     13950109.28
#Sta/Elev= 30
  4408.8 2017.36  4533.2 2007.66  4590.7 2001.28  4653.7 1997.79  4707.3 1991.49
  4712.8 1988.72  4741.6 1983.57  4782.7 1980.43  4788.2 1977.08  4795.8 1976.14
  4811.5 1975.68  4817.7 1978.53  4834.8 1978.23  4872.3 1962.40  4910.2 1955.78
  4916.1 1952.71  4933.6 1948.85  4939.0 1945.59  4952.4 1946.34  4992.0 1943.12
  4992.5 1942.62  5008.2 1943.12  5038.2 1947.59  5043.8 1946.08  5065.7 1947.10
  5087.6 1958.12  5153.3 1972.99  5198.8 1979.83  5406.5 1989.67  5432.5 1990.27
#Mann=4,-1,0
  4408.8    0.07       0  4992.0    0.05       0  5008.2    0.07       0
  5406.5   0.035       0
Bank Sta=4992,5008.2
Exp/Cntr=0.3,0.1

Type RM Length L Ch R = 1,26049,475,475,475
BEGIN DESCRIPTION:
Honey Creek 50.0
END DESCRIPTION:
XS GIS Cut Line= 3
      1848374.98     13950574.97      1848225.00     13950325.00
      1848075.04     13950175.04
#Sta/Elev= 30
  4712.4 1997.88  4726.0 1997.08  4747.4 1993.31  4784.3 1982.06  4794.0 1980.90
  4805.7 1977.85  4821.2 1971.09  4829.0 1966.60  4842.6 1962.34  4852.3 1956.83
  4864.0 1948.64  4873.7 1946.69  4895.1 1946.40  4900.9 1944.80  4910.6 1946.08
  4932.0 1946.31  4959.2 1944.14  4972.5 1942.03  4973.0 1941.53  4988.7 1942.03
  4990.6 1944.70  4996.1 1947.38  5001.0 1950.97  5007.5 1950.97  5018.1 1956.98
  5032.2 1960.88  5074.6 1968.16  5102.9 1974.10  5159.5 1980.39  5216.0 1982.86
#Mann=4,-1,0
  4712.4     0.1       0  4972.5    0.05       0  4988.7     0.1       0
  4990.6    0.07       0
Bank Sta=4972.5,4988.7
Exp/Cntr=0.3,0.1

Type RM Length L Ch R = 1,25574,418,418,418
BEGIN DESCRIPTION:
Honey Creek 49.0
END DESCRIPTION:
XS GIS Cut Line= 3
      1848774.98     13950324.97      1848625.00     13950125.00
      1848475.00     13949975.00
#Sta/Elev= 30
  4754.6 1990.04  4804.6 1982.60  4847.3 1971.18  4854.6 1967.30  4861.9 1964.48
  4876.4 1954.98  4882.7 1952.24  4891.0 1947.48  4904.6 1944.99  4918.1 1944.50
  4932.7 1945.03  4952.7 1944.18  4982.7 1940.94  4989.1 1939.12  4989.6 1938.62
  5004.9 1938.62  5005.4 1939.12  5032.9 1943.47  5047.0 1944.43  5061.1 1946.71
  5075.3 1952.30  5089.4 1955.66  5103.6 1957.26  5126.0 1961.30  5160.1 1966.34
  5174.3 1969.87  5181.3 1970.24  5188.4 1971.55  5215.3 1972.49  5216.7 1972.49
#Mann=6,-1,0
  4754.6     0.1       0  4952.7    0.07       0  4989.1    0.05       0
  5005.4    0.07       0  5126.0     0.1       0  5215.3    0.07       0
Bank Sta=4989.1,5005.4
Exp/Cntr=0.3,0.1

Type RM Length L Ch R = 1,25156,470,470,470
BEGIN DESCRIPTION:
Honey Creek 48.0
END DESCRIPTION:
XS GIS Cut Line= 3
      1849025.02     13950075.04      1848925.00     13949875.00
      1848624.98     13949774.99
#Sta/Elev= 30
  4776.6 1981.19  4799.0 1980.52  4813.0 1979.19  4821.4 1975.99  4829.8 1974.94
  4835.3 1970.34  4843.7 1968.42  4852.1 1964.86  4860.5 1955.63  4872.9 1948.81
  4880.1 1945.46  4898.1 1942.21  4924.8 1941.63  4969.5 1939.31  4977.9 1938.37
  4983.7 1935.41  4984.2 1934.91  4999.5 1934.91  5000.0 1935.41  5021.3 1938.45
  5074.0 1938.92  5084.6 1939.68  5095.1 1941.64  5116.2 1948.77  5147.8 1954.15
  5163.3 1954.97  5221.6 1959.88  5274.3 1965.71  5305.9 1970.51  5316.5 1971.51
#Mann=6,-1,0
  4776.6    0.07       0  4872.9     0.1       0  4898.1    0.07       0
  4983.7    0.05       0  5000.0    0.07       0  5163.3     0.1       0
Bank Sta=4983.7,5000
Exp/Cntr=0.3,0.1