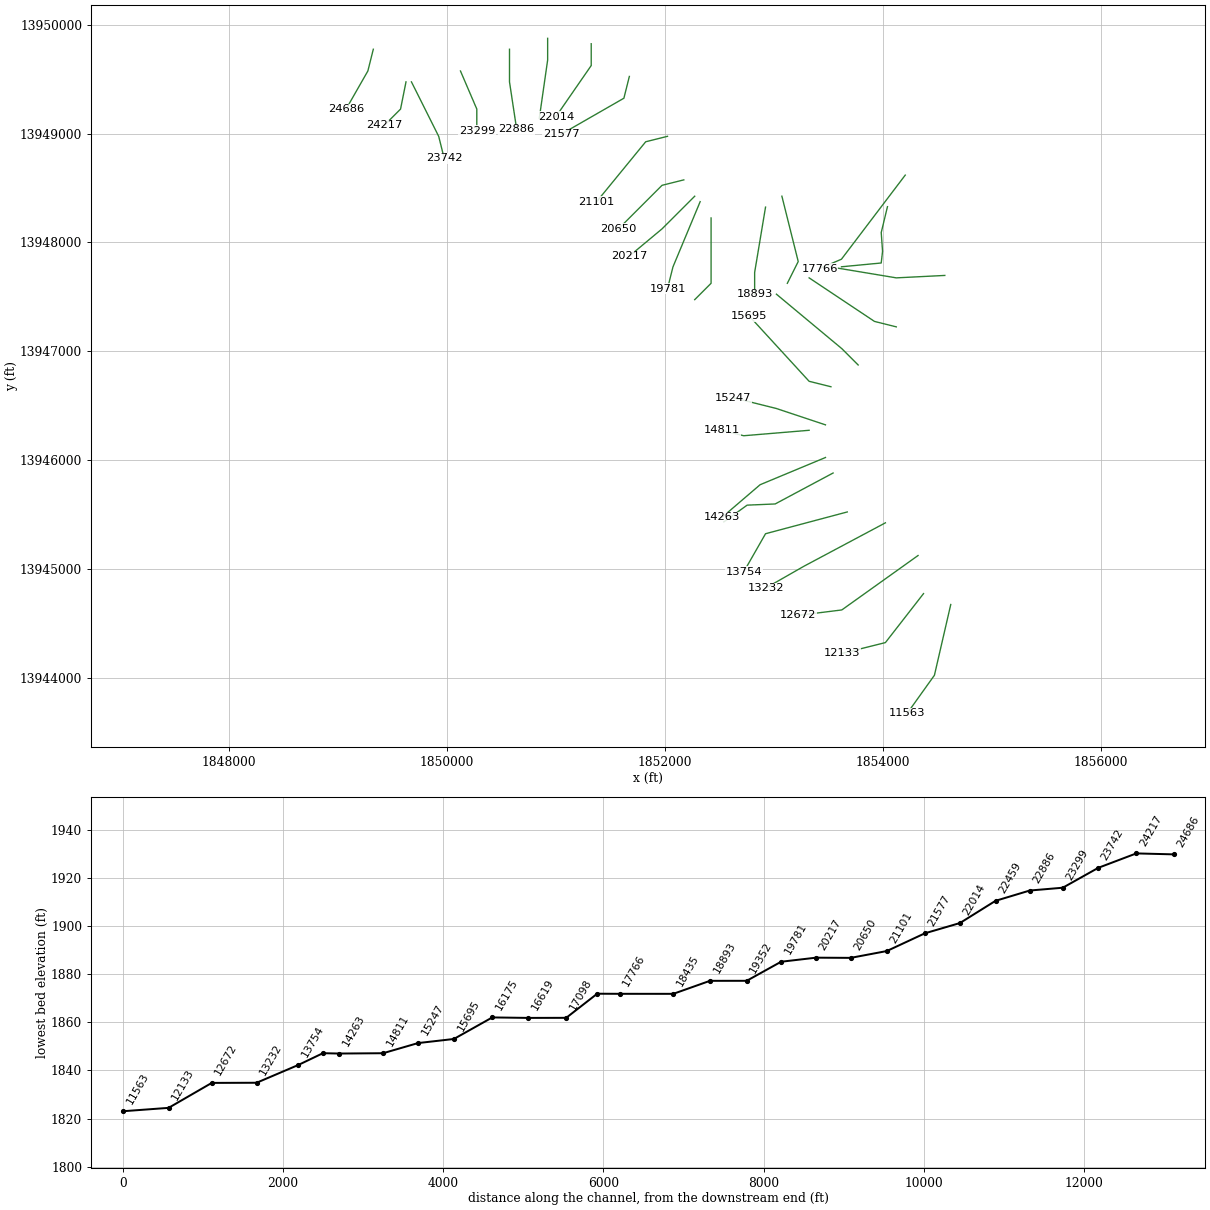
HEC-RAS study Honey Creek.prj: Honey Creek Base Level Engineering

--- Honey Creek.g01 (geometry) --- (continued)

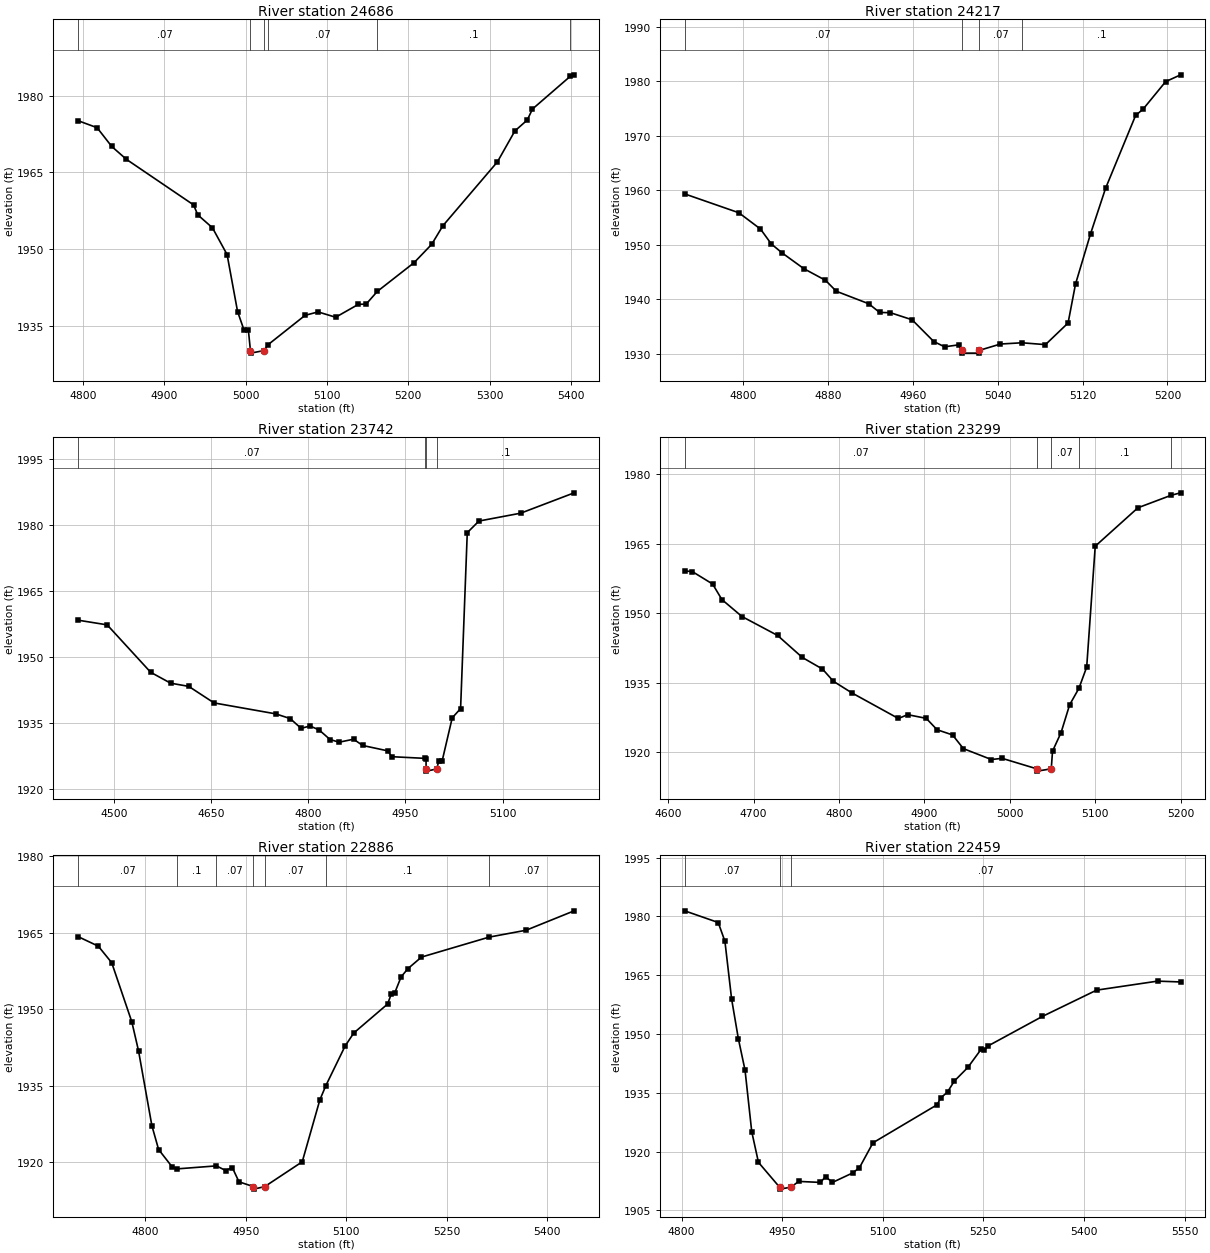
Type RM Length L Ch R = 1,24686,469,469,469
BEGIN DESCRIPTION:
Honey Creek 47.0
END DESCRIPTION:
XS GIS Cut Line= 3
      1849325.00     13949774.98      1849275.00     13949575.00
      1849074.98     13949224.96
#Sta/Elev= 30
  4794.4 1975.11  4817.6 1973.75  4835.6 1970.08  4853.7 1967.56  4936.1 1958.67
  4941.3 1956.72  4959.3 1954.20  4977.3 1948.97  4990.2 1937.82  4998.0 1934.27
  5003.4 1934.27  5006.0 1930.21  5006.5 1929.71  5022.5 1930.21  5027.7 1931.36
  5073.2 1937.10  5089.1 1937.76  5110.7 1936.72  5138.7 1939.25  5148.1 1939.28
  5161.9 1941.77  5207.1 1947.39  5228.7 1950.97  5242.4 1954.59  5309.4 1967.07
  5330.9 1973.12  5346.1 1975.25  5352.5 1977.40  5399.0 1983.80  5403.7 1984.08
#Mann=6,-1,0
  4794.4    0.07       0  5006.0    0.05       0  5022.5    0.07       0
  5027.7    0.07       0  5161.9     0.1       0  5399.0    0.07       0
Bank Sta=5006,5022.5
Exp/Cntr=0.3,0.1

Type RM Length L Ch R = 1,24217,475,475,475
BEGIN DESCRIPTION:
Honey Creek 46.0
END DESCRIPTION:
XS GIS Cut Line= 3
      1849625.01     13949475.04      1849575.00     13949225.00
      1849425.01     13949075.01
#Sta/Elev= 30
  4745.3 1959.34  4796.3 1955.88  4816.7 1952.89  4826.9 1950.15  4837.1 1948.50
  4857.5 1945.62  4877.9 1943.48  4888.1 1941.47  4918.7 1939.17  4928.9 1937.58
  4939.1 1937.53  4959.5 1936.23  4979.9 1932.24  4990.1 1931.27  5003.8 1931.64
  5006.2 1930.61  5006.7 1930.11  5022.2 1930.11  5022.7 1930.61  5042.7 1931.78
  5063.0 1932.01  5085.1 1931.67  5106.4 1935.64  5113.4 1942.78  5127.6 1952.04
  5141.7 1960.36  5170.0 1973.74  5177.1 1974.91  5198.3 1979.95  5212.4 1981.20
#Mann=4,-1,0
  4745.3    0.07       0  5006.2    0.05       0  5022.7    0.07       0
  5063.0     0.1       0
Bank Sta=5006.2,5022.7
Exp/Cntr=0.3,0.1

Type RM Length L Ch R = 1,23742,443,443,443
BEGIN DESCRIPTION:
Honey Creek 45.0
END DESCRIPTION:
XS GIS Cut Line= 3
      1849675.02     13949474.97      1849925.00     13948975.00
      1849974.99     13948775.03
#Sta/Elev= 30
  4445.1 1958.41  4489.8 1957.35  4556.9 1946.58  4587.6 1944.11  4615.6 1943.38
  4654.7 1939.62  4749.7 1937.14  4772.1 1936.07  4788.9 1933.85  4802.8 1934.38
  4816.8 1933.48  4833.6 1931.31  4847.6 1930.70  4869.9 1931.38  4883.9 1929.96
  4923.0 1928.72  4928.6 1927.41  4979.9 1927.03  4981.7 1926.93  4981.8 1924.63
  4982.3 1924.13  4998.5 1924.63  5001.3 1926.54  5006.7 1926.54  5022.1 1936.24
  5035.0 1938.33  5045.3 1978.29  5063.3 1980.93  5127.8 1982.72  5210.2 1987.34
#Mann=4,-1,0
  4445.1    0.07       0  4979.9     0.1       0  4981.8    0.05       0
  4998.5     0.1       0
Bank Sta=4981.8,4998.5
Exp/Cntr=0.3,0.1

Type RM Length L Ch R = 1,23299,413,413,413
BEGIN DESCRIPTION:
Honey Creek 44.0
END DESCRIPTION:
XS GIS Cut Line= 3
      1850124.99     13949575.03      1850275.00     13949225.00
      1850275.00     13949025.02
#Sta/Elev= 30
  4619.2 1959.13  4628.3 1958.96  4651.9 1956.29  4662.8 1952.93  4686.3 1949.27
  4728.0 1945.18  4757.0 1940.42  4780.6 1937.92  4793.3 1935.29  4815.1 1932.76
  4869.5 1927.24  4880.3 1928.07  4902.1 1927.27  4914.8 1924.81  4932.9 1923.69
  4945.6 1920.73  4978.3 1918.38  4991.0 1918.63  5031.5 1916.37  5032.0 1915.87
  5048.5 1916.37  5050.0 1920.19  5060.0 1924.20  5070.0 1930.19  5080.9 1933.76
  5090.0 1938.35  5100.0 1964.46  5150.0 1972.76  5189.2 1975.48  5200.0 1975.99
#Mann=5,-1,0
  4619.2    0.07       0  5031.5    0.05       0  5048.5    0.07       0
  5080.9     0.1       0  5189.2    0.07       0
Bank Sta=5031.5,5048.5
Exp/Cntr=0.3,0.1

Type RM Length L Ch R = 1,22886,427,427,427
BEGIN DESCRIPTION:
Honey Creek 43.0
END DESCRIPTION:
XS GIS Cut Line= 3
      1850575.00     13949775.01      1850575.00     13949475.00
      1850640.77     13949039.65
#Sta/Elev= 30
  4699.7 1964.20  4729.7 1962.34  4749.7 1959.10  4779.7 1947.51  4789.7 1941.84
  4809.7 1927.12  4819.7 1922.47  4839.7 1919.10  4847.2 1918.67  4906.1 1919.26
  4919.7 1918.35  4929.7 1918.93  4939.7 1916.13  4961.2 1915.20  4961.7 1914.70
  4978.2 1915.20  5034.1 1920.06  5060.4 1932.20  5069.4 1935.01  5098.0 1942.73
  5111.0 1945.31  5161.5 1950.99  5166.8 1952.87  5171.9 1953.09  5181.7 1956.32
  5191.9 1957.94  5212.1 1960.20  5312.9 1964.11  5368.4 1965.47  5440.0 1969.27
#Mann=7,-1,0
  4699.7    0.07       0  4847.2     0.1       0  4906.1    0.07       0
  4961.2    0.05       0  4978.2    0.07       0  5069.4     0.1       0
  5312.9    0.07       0
Bank Sta=4961.2,4978.2
Exp/Cntr=0.3,0.1

Type RM Length L Ch R = 1,22459,445,445,445
BEGIN DESCRIPTION:
Honey Creek 42.0
END DESCRIPTION:
XS GIS Cut Line= 3
      1850925.00     13949874.96      1850925.00     13949675.00
      1850848.39     13949140.92
#Sta/Elev= 30
  4804.7 1981.41  4854.7 1978.43  4864.7 1973.64  4874.7 1958.89  4884.7 1948.83
  4894.7 1940.77  4904.7 1925.08  4914.7 1917.26  4946.2 1910.93  4946.7 1910.43
  4963.2 1910.93  4974.7 1912.40  5007.2 1912.14  5014.8 1913.64  5024.9 1912.13
  5055.2 1914.56  5065.3 1915.90  5085.5 1922.25  5181.1 1931.95  5186.5 1933.68
  5196.6 1935.20  5206.7 1937.98  5226.9 1941.46  5246.6 1946.07  5251.7 1945.85
  5257.2 1946.96  5338.0 1954.47  5418.9 1961.18  5509.8 1963.48  5544.2 1963.27
#Mann=3,-1,0
  4804.7    0.07       0  4946.2    0.05       0  4963.2    0.07       0
Bank Sta=4946.2,4963.2
Exp/Cntr=0.3,0.1

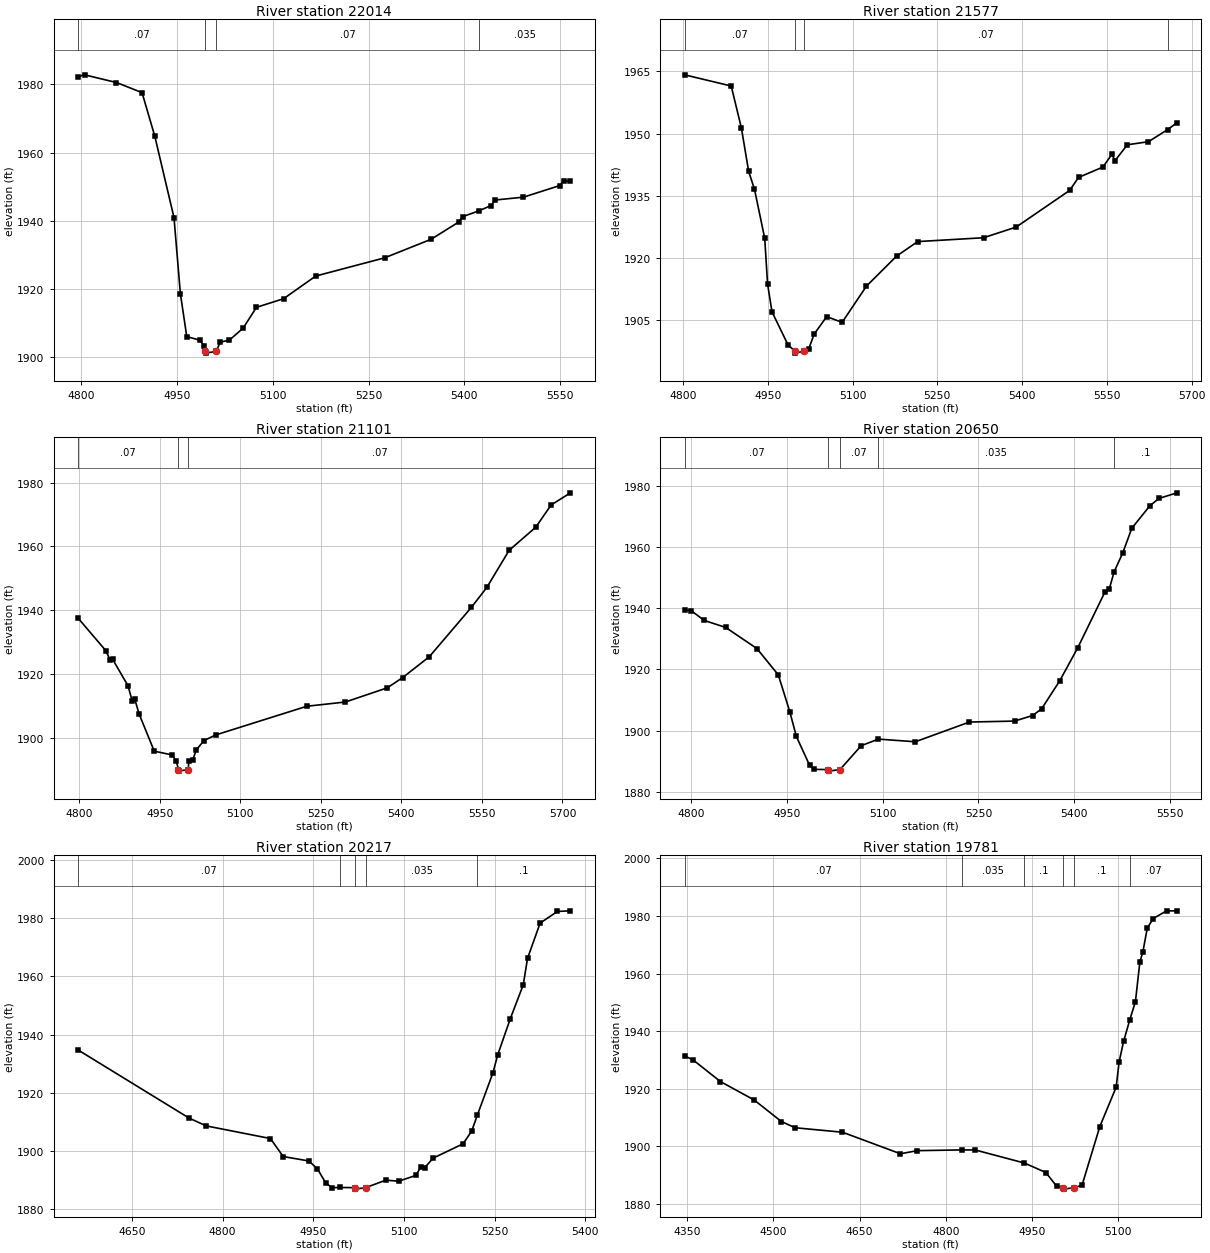
Type RM Length L Ch R = 1,22014,437,437,437
BEGIN DESCRIPTION:
Honey Creek 41.0
END DESCRIPTION:
XS GIS Cut Line= 3
      1851325.00     13949825.05      1851325.00     13949625.00
      1851000.90     13949155.56
#Sta/Elev= 30
  4795.5 1982.29  4805.5 1982.80  4855.5 1980.54  4895.5 1977.58  4915.5 1964.76
  4945.5 1940.92  4955.5 1918.64  4965.5 1906.04  4985.5 1905.03  4993.0 1903.26
  4994.4 1901.70  4994.9 1901.20  5011.5 1901.70  5017.9 1904.44  5032.0 1904.98
  5053.7 1908.53  5074.6 1914.63  5117.1 1917.16  5167.3 1923.80  5275.0 1929.13
  5347.9 1934.58  5391.0 1939.62  5397.1 1941.20  5422.4 1942.90  5441.7 1944.47
  5447.8 1946.09  5492.4 1946.93  5549.2 1950.33  5555.3 1951.70  5566.0 1951.60
#Mann=4,-1,0
  4795.5    0.07       0  4994.4    0.05       0  5011.5    0.07       0
  5422.4   0.035       0
Bank Sta=4994.4,5011.5
Exp/Cntr=0.3,0.1

Type RM Length L Ch R = 1,21577,476,476,476
BEGIN DESCRIPTION:
Honey Creek 40.0
END DESCRIPTION:
XS GIS Cut Line= 3
      1851675.01     13949525.04      1851625.00     13949325.00
      1851048.40     13948993.71
#Sta/Elev= 30
  4802.7 1964.19  4885.2 1961.49  4903.2 1951.36  4916.1 1940.85  4926.4 1936.54
  4944.5 1924.69  4949.6 1913.61  4957.4 1906.92  4985.7 1898.95  4997.8 1897.45
  4998.3 1896.95  5014.9 1897.45  5022.6 1898.04  5032.0 1901.55  5054.2 1905.77
  5081.5 1904.38  5124.6 1913.15  5177.8 1920.38  5215.2 1923.90  5331.8 1924.83
  5389.5 1927.41  5484.1 1936.26  5499.9 1939.40  5543.0 1941.91  5558.8 1944.95
  5564.6 1943.48  5586.2 1947.29  5623.5 1948.03  5657.5 1950.95  5673.9 1952.60
#Mann=4,-1,0
  4802.7    0.07       0  4997.8    0.05       0  5014.9    0.07       0
  5657.5   0.035       0
Bank Sta=4997.8,5014.9
Exp/Cntr=0.3,0.1

Type RM Length L Ch R = 1,21101,451,451,451
BEGIN DESCRIPTION:
Honey Creek 39.0
END DESCRIPTION:
XS GIS Cut Line= 3
      1852024.98     13948974.99      1851825.00     13948925.00
      1851374.98     13948374.97
#Sta/Elev= 30
  4798.1 1937.50  4849.6 1927.34  4857.3 1924.54  4862.5 1924.57  4890.8 1916.39
  4898.6 1911.67  4903.7 1912.04  4911.5 1907.55  4939.8 1895.84  4973.3 1894.64
  4981.0 1892.72  4984.8 1890.08  4985.3 1889.58  5003.1 1890.08  5004.2 1892.67
  5011.4 1893.06  5017.9 1896.15  5032.2 1899.15  5054.5 1900.93  5223.9 1909.91
  5295.7 1911.24  5373.9 1915.69  5402.6 1918.91  5452.1 1925.44  5530.4 1940.90
  5559.1 1947.13  5600.7 1958.78  5650.3 1966.03  5679.0 1973.00  5714.9 1976.80
#Mann=3,-1,0
  4798.1    0.07       0  4984.8    0.05       0  5003.1    0.07       0
Bank Sta=4984.8,5003.1
Exp/Cntr=0.3,0.1

Type RM Length L Ch R = 1,20650,433,433,433
BEGIN DESCRIPTION:
Honey Creek 38.0
END DESCRIPTION:
XS GIS Cut Line= 3
      1852175.01     13948575.00      1851975.00     13948525.00
      1851575.03     13948125.03
#Sta/Elev= 30
  4789.3 1939.38  4799.6 1939.22  4820.2 1936.01  4853.7 1933.73  4902.7 1926.82
  4936.2 1918.22  4954.2 1906.20  4964.5 1898.11  4985.2 1888.70  4992.9 1887.33
  5014.6 1887.25  5015.1 1886.75  5032.9 1887.25  5066.2 1895.07  5093.2 1897.22
  5151.0 1896.35  5235.9 1902.80  5306.6 1903.11  5334.9 1904.93  5349.0 1907.11
  5377.3 1916.23  5405.6 1927.04  5448.0 1945.18  5455.1 1946.27  5462.7 1951.91
  5476.3 1958.12  5490.4 1966.14  5518.7 1973.49  5532.9 1975.89  5561.1 1977.74
#Mann=5,-1,0
  4789.3    0.07       0  5014.6    0.05       0  5032.9    0.07       0
  5093.2   0.035       0  5462.7     0.1       0
Bank Sta=5014.6,5032.9
Exp/Cntr=0.3,0.1

Type RM Length L Ch R = 1,20217,436,436,436
BEGIN DESCRIPTION:
Honey Creek 37.0
END DESCRIPTION:
XS GIS Cut Line= 3
      1852274.98     13948424.98      1851975.00     13948125.00
      1851674.96     13947874.97
#Sta/Elev= 30
  4560.9 1934.69  4744.7 1911.25  4773.0 1908.58  4879.1 1904.24  4900.3 1898.04
  4942.7 1896.52  4956.9 1893.82  4971.0 1888.83  4981.6 1887.33  4993.9 1887.40
  5018.3 1887.33  5018.8 1886.83  5036.6 1887.33  5070.4 1889.93  5091.2 1889.54
  5119.9 1891.55  5127.7 1894.33  5134.2 1894.14  5148.5 1897.51  5198.0 1902.42
  5212.3 1906.83  5221.6 1912.29  5247.4 1926.83  5255.2 1932.95  5276.1 1945.44
  5297.6 1957.13  5304.7 1966.25  5325.5 1978.36  5354.2 1982.37  5375.7 1982.58
#Mann=5,-1,0
  4560.9    0.07       0  4993.9   0.035       0  5018.3   0.035       0
  5036.6   0.035       0  5221.6     0.1       0
Bank Sta=5018.3,5036.6
Exp/Cntr=0.3,0.1

Type RM Length L Ch R = 1,19781,429,429,429
BEGIN DESCRIPTION:
Honey Creek 36.0
END DESCRIPTION:
XS GIS Cut Line= 3
      1852324.99     13948374.98      1852075.00     13947775.00
      1852025.01     13947575.03
#Sta/Elev= 30
  4345.6 1931.39  4360.2 1930.03  4407.9 1922.50  4466.4 1916.12  4514.0 1908.61
  4537.9 1906.45  4620.2 1904.90  4721.0 1897.42  4750.2 1898.50  4828.6 1898.76
  4851.0 1898.74  4936.6 1894.20  4973.9 1890.90  4992.9 1886.07  5004.5 1885.64
  5005.0 1885.14  5022.8 1885.64  5036.8 1886.51  5067.7 1906.87  5096.1 1920.55
  5101.2 1929.25  5109.0 1936.42  5119.8 1943.94  5129.6 1950.23  5137.3 1963.98
  5142.5 1967.47  5150.2 1975.75  5160.5 1979.09  5183.7 1981.78  5201.7 1981.75
#Mann=6,-1,0
  4345.6    0.07       0  4828.6   0.035       0  4936.6     0.1       0
  5004.5    0.05       0  5022.8     0.1       0  5119.8    0.07       0
Bank Sta=5004.5,5022.8
Exp/Cntr=0.3,0.1

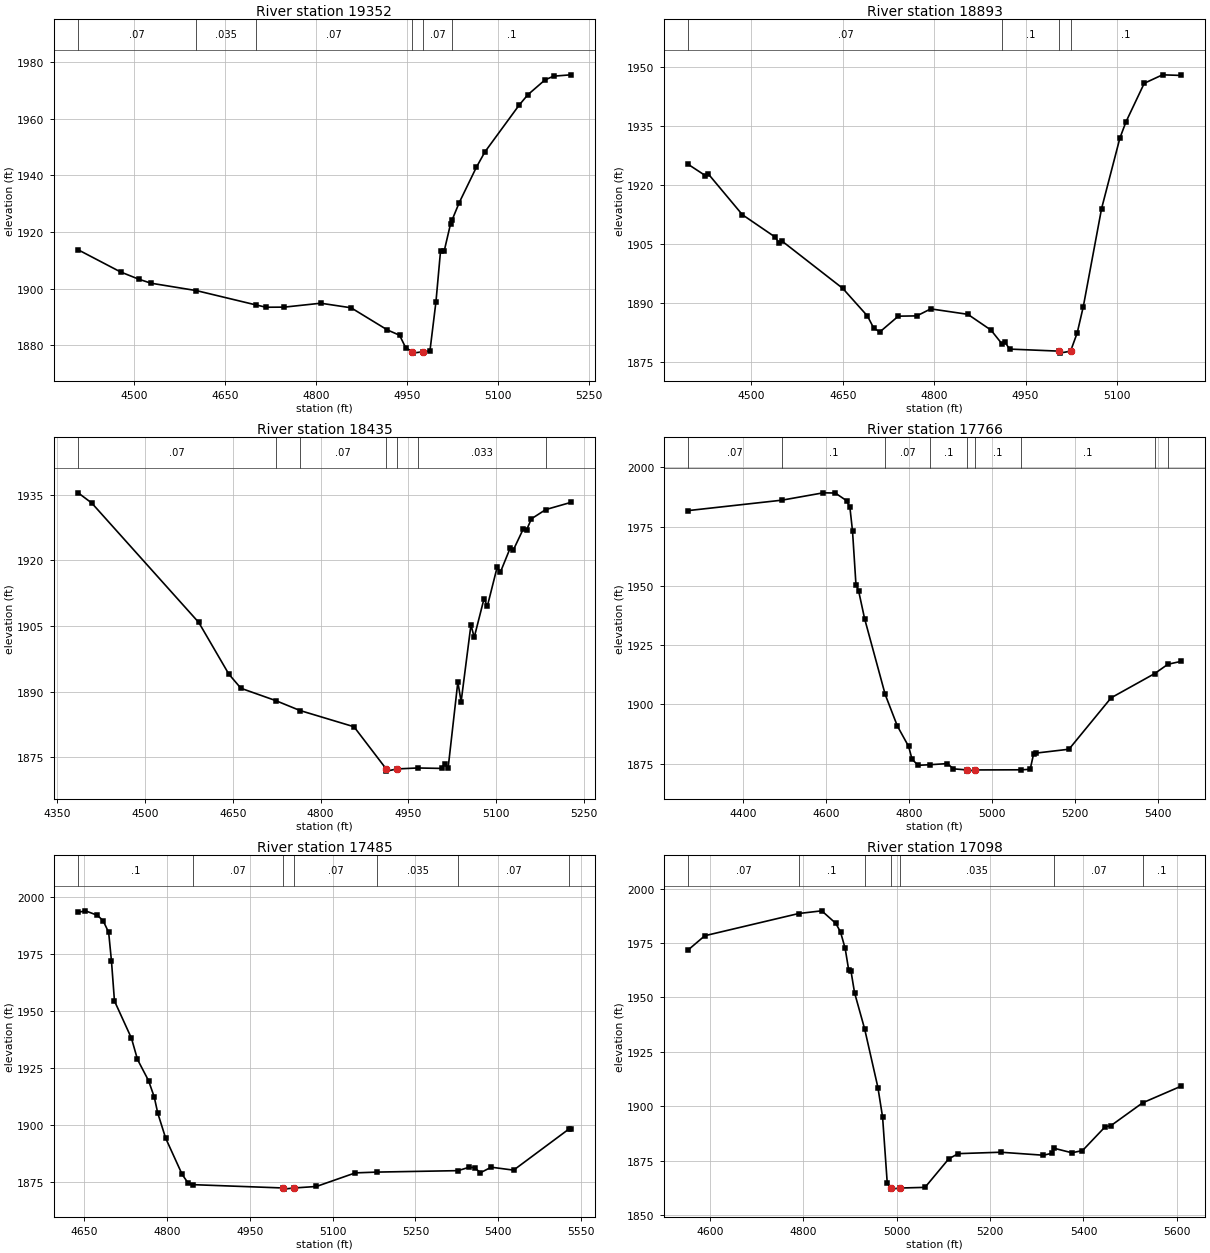
Type RM Length L Ch R = 1,19352,459,459,459
BEGIN DESCRIPTION:
Honey Creek 35.0
END DESCRIPTION:
XS GIS Cut Line= 3
      1852425.00     13948224.98      1852425.00     13947625.00
      1852275.01     13947475.01
#Sta/Elev= 30
  4407.8 1913.71  4477.8 1905.88  4507.8 1903.33  4527.8 1901.92  4602.8 1899.30
  4701.1 1894.24  4717.8 1893.43  4747.8 1893.47  4807.8 1894.85  4857.8 1893.24
  4917.8 1885.40  4937.8 1883.55  4947.8 1879.17  4958.6 1877.73  4959.1 1877.23
  4976.9 1877.73  4987.8 1877.91  4997.8 1895.41  5005.3 1913.22  5011.3 1913.22
  5021.9 1922.94  5024.7 1924.40  5036.1 1930.34  5064.3 1942.79  5078.5 1948.27
  5135.1 1964.83  5149.2 1968.43  5177.5 1973.67  5191.6 1975.00  5219.9 1975.48
#Mann=6,-1,0
  4407.8    0.07       0  4602.8   0.035       0  4701.1    0.07       0
  4958.6    0.05       0  4976.9    0.07       0  5024.7     0.1       0
Bank Sta=4958.6,4976.9
Exp/Cntr=0.3,0.1

Type RM Length L Ch R = 1,18893,458,458,458
BEGIN DESCRIPTION:
Honey Creek 34.0
END DESCRIPTION:
XS GIS Cut Line= 3
      1852925.00     13948325.01      1852825.00     13947725.00
      1852825.00     13947524.99
#Sta/Elev= 30
  4396.5 1925.16  4424.4 1922.33  4429.5 1922.71  4485.2 1912.39  4538.4 1906.77
  4546.0 1905.17  4551.1 1905.59  4650.0 1893.67  4690.5 1886.66  4700.6 1883.64
  4710.8 1882.59  4741.2 1886.61  4771.6 1886.68  4794.4 1888.46  4855.3 1887.08
  4893.3 1883.07  4912.1 1879.42  4916.1 1880.07  4923.7 1878.25  5005.6 1877.72
  5006.1 1877.22  5023.9 1877.72  5034.8 1882.36  5044.8 1889.04  5074.8 1913.95
  5104.8 1931.83  5114.8 1935.96  5144.8 1945.77  5174.8 1947.92  5204.8 1947.77
#Mann=4,-1,0
  4396.5    0.07       0  4912.1     0.1       0  5005.6    0.05       0
  5023.9     0.1       0
Bank Sta=5005.6,5023.9
Exp/Cntr=0.3,0.1

Type RM Length L Ch R = 1,18435,669,669,669
BEGIN DESCRIPTION:
Honey Creek 33.0
END DESCRIPTION:
XS GIS Cut Line= 3
      1853074.99     13948425.03      1853225.00     13947825.00
      1853125.00     13947625.01
#Sta/Elev= 30
  4385.5 1935.41  4408.7 1933.08  4591.7 1905.79  4643.2 1893.97  4663.8 1890.75
  4723.0 1887.95  4764.8 1885.67  4857.1 1881.96  4912.2 1872.32  4912.7 1871.82
  4930.8 1872.32  4966.0 1872.54  5006.8 1872.44  5012.4 1873.50  5018.0 1872.43
  5034.7 1892.20  5040.3 1887.69  5057.1 1905.24  5062.7 1902.38  5079.5 1911.24
  5085.1 1909.48  5101.8 1918.36  5107.4 1917.26  5124.2 1922.79  5129.8 1922.41
  5146.6 1927.16  5152.1 1926.89  5160.5 1929.48  5185.0 1931.58  5227.6 1933.21
#Mann=7,-1,0
  4385.5    0.07       0  4723.0   0.035       0  4764.8    0.07       0
  4912.2   0.033       0  4930.8    0.07       0  4966.0   0.033       0
  5185.0     0.1       0
Bank Sta=4912.2,4930.8
Exp/Cntr=0.3,0.1

Type RM Length L Ch R = 1,17766,281,281,281
BEGIN DESCRIPTION:
Honey Creek 32.1
END DESCRIPTION:
XS GIS Cut Line= 3
      1854207.11     13948618.57      1853621.50     13947846.12
      1853420.38     13947760.57
#Sta/Elev= 30
  4268.1 1981.77  4493.9 1986.16  4593.5 1989.26  4622.6 1989.18  4649.7 1985.97
  4657.9 1983.13  4664.2 1973.12  4672.5 1950.57  4678.8 1947.98  4693.3 1936.20
  4743.0 1904.18  4772.4 1890.85  4799.6 1882.23  4807.7 1876.88  4822.3 1874.28
  4851.9 1874.55  4893.0 1875.00  4907.6 1872.79  4940.9 1872.33  4941.4 1871.83
  4959.6 1872.33  5071.7 1872.39  5092.7 1872.59  5100.8 1878.94  5107.3 1879.45
  5186.3 1881.07  5288.0 1902.77  5393.0 1912.99  5424.9 1916.92  5456.0 1918.12
#Mann=9,-1,0
  4268.1    0.07       0  4493.9     0.1       0  4743.0    0.07       0
  4851.9     0.1       0  4940.9    0.05       0  4959.6     0.1       0
  5071.7     0.1       0  5393.0   0.033       0  5424.9     0.1       0
Bank Sta=4940.9,4959.6
Exp/Cntr=0.3,0.1

Type RM Length L Ch R = 1,17485,387,387,387
BEGIN DESCRIPTION:
Honey Creek 32.2
END DESCRIPTION:
XS GIS Cut Line= 5
      1854044.06     13948328.86      1853986.78     13948091.06
      1853998.94     13947919.19      1853986.78     13947811.55
      1853622.16     13947776.82
#Sta/Elev= 30
  4639.4 1993.18  4652.6 1993.84  4674.2 1991.88  4684.5 1989.53  4694.6 1984.40
  4699.7 1971.76  4705.1 1954.33  4735.9 1937.98  4746.8 1928.69  4766.8 1919.41
  4777.1 1912.25  4783.5 1905.16  4797.7 1894.25  4827.6 1878.32  4838.8 1874.40
  4847.1 1873.83  5011.0 1872.37  5011.5 1871.87  5029.7 1872.37  5070.6 1873.03
  5141.0 1878.99  5180.9 1879.34  5327.2 1879.97  5347.2 1881.47  5357.3 1881.29
  5367.3 1879.02  5387.1 1881.48  5427.6 1880.19  5528.3 1898.30  5530.9 1898.30
#Mann=7,-1,0
  4639.4     0.1       0  4847.1    0.07       0  5011.0    0.05       0
  5029.7    0.07       0  5180.9   0.035       0  5327.2    0.07       0
  5528.3     0.1       0
Bank Sta=5011,5029.7
Exp/Cntr=0.3,0.1

Type RM Length L Ch R = 1,17098,479,479,479
BEGIN DESCRIPTION:
Honey Creek 32.0
END DESCRIPTION:
XS GIS Cut Line= 3
      1854570.35     13947697.29      1854125.00     13947675.00
      1853524.99     13947775.00
#Sta/Elev= 30
  4554.1 1971.92  4589.5 1978.40  4790.6 1988.62  4839.8 1989.85  4869.8 1984.09
  4879.9 1980.14  4889.9 1972.53  4897.4 1962.68  4902.4 1962.09  4909.9 1952.25
  4931.5 1935.59  4960.0 1908.58  4970.0 1894.97  4980.0 1864.53  4988.2 1862.36
  4988.7 1861.86  5006.9 1862.36  5060.8 1862.67  5111.5 1875.76  5131.8 1878.18
  5223.0 1878.83  5314.3 1877.45  5332.0 1878.34  5337.7 1880.62  5375.1 1878.58
  5397.9 1879.58  5446.1 1890.47  5458.8 1891.06  5526.6 1901.55  5608.3 1909.14
#Mann=7,-1,0
  4554.1    0.07       0  4790.6     0.1       0  4931.5   0.035       0
  4988.2   0.035       0  5006.9   0.035       0  5337.7    0.07       0
  5526.6     0.1       0
Bank Sta=4988.2,5006.9
Exp/Cntr=0.3,0.1

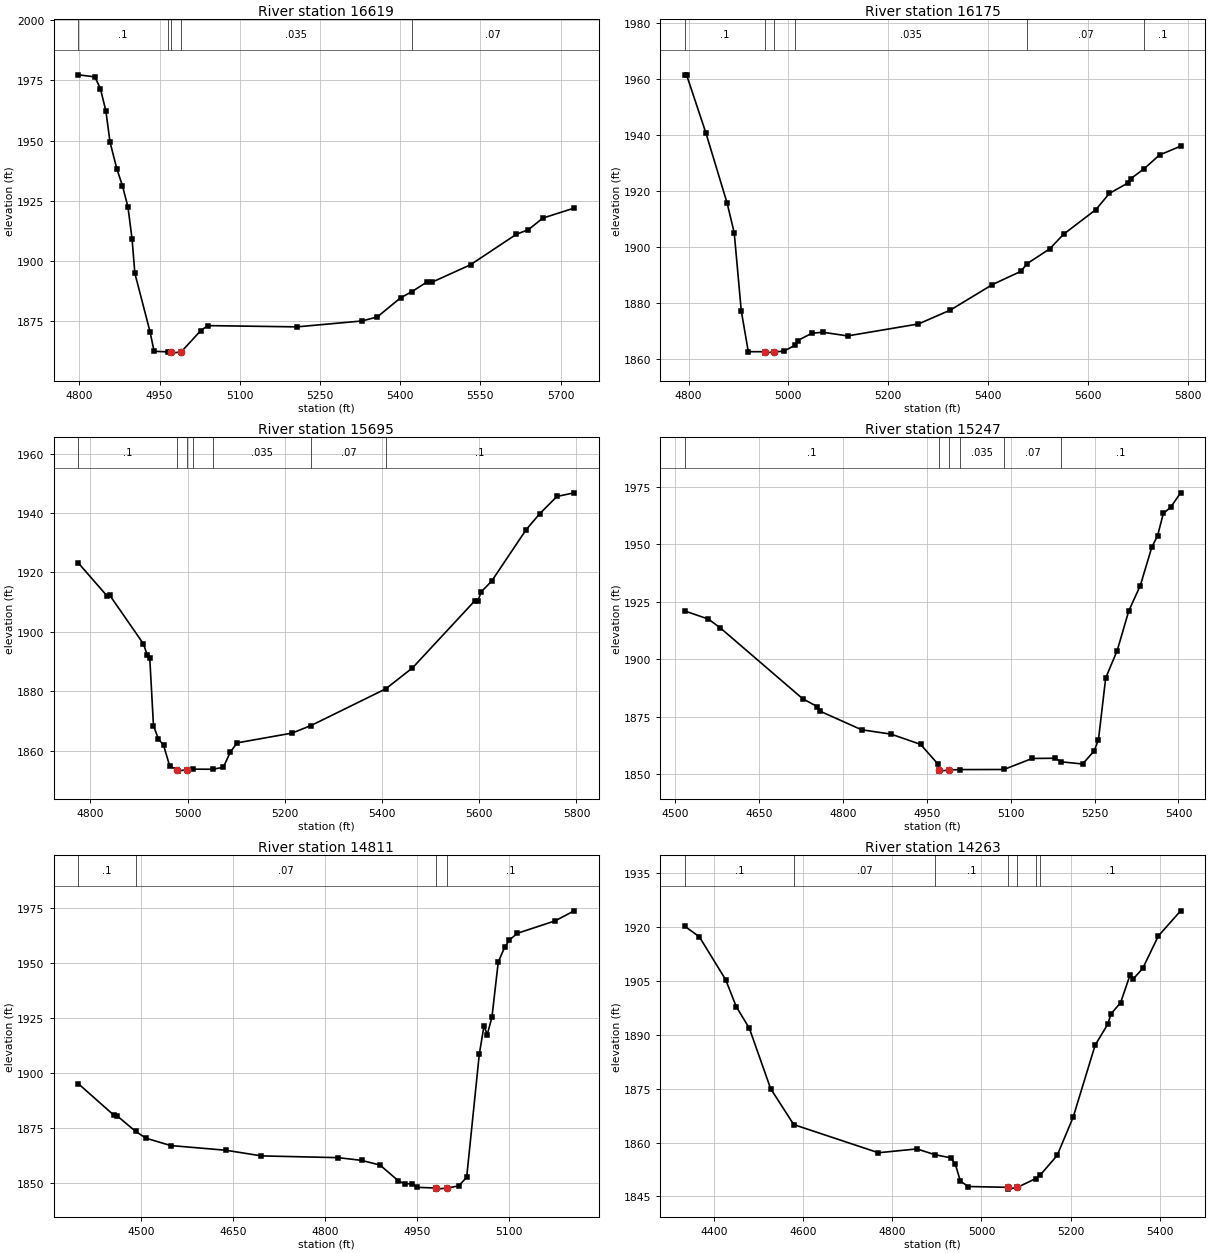
Type RM Length L Ch R = 1,16619,444,444,444
BEGIN DESCRIPTION:
Honey Creek 31.0
END DESCRIPTION:
XS GIS Cut Line= 3
      1854125.00     13947225.00      1853925.00     13947275.00
      1853324.97     13947675.02
#Sta/Elev= 30
  4798.2 1977.32  4829.1 1976.47  4839.4 1971.63  4849.7 1962.34  4857.5 1949.33
  4870.4 1938.18  4880.7 1931.26  4891.0 1922.49  4898.7 1909.20  4903.9 1894.98
  4932.2 1870.78  4939.9 1862.59  4965.5 1862.36  4971.8 1862.33  4972.3 1861.83
  4990.5 1862.33  5026.9 1871.11  5040.4 1873.25  5207.2 1872.73  5328.9 1875.18
  5357.4 1876.86  5401.0 1884.80  5421.7 1887.30  5450.5 1891.39  5459.6 1891.26
  5531.7 1898.51  5617.3 1911.14  5639.8 1913.04  5666.9 1917.86  5725.5 1922.02
#Mann=5,-1,0
  4798.2     0.1       0  4965.5   0.035       0  4971.8   0.035       0
  4990.5   0.035       0  5421.7    0.07       0
Bank Sta=4971.8,4990.5
Exp/Cntr=0.3,0.1

Type RM Length L Ch R = 1,16175,480,480,480
BEGIN DESCRIPTION:
Honey Creek 30.0
END DESCRIPTION:
XS GIS Cut Line= 3
      1853774.98     13946875.02      1853625.00     13947025.00
      1853025.02     13947524.98
#Sta/Elev= 30
  4792.5 1961.60  4796.0 1961.60  4834.9 1940.73  4877.3 1915.68  4891.5 1905.09
  4905.6 1877.15  4919.7 1862.55  4952.8 1862.53  4953.3 1862.03  4971.6 1862.53
  4990.5 1862.69  5012.7 1864.79  5018.3 1866.48  5046.9 1869.15  5069.0 1869.50
  5118.5 1868.19  5260.4 1872.46  5324.2 1877.42  5408.8 1886.57  5466.1 1891.33
  5477.7 1894.01  5523.3 1899.32  5551.3 1904.59  5615.8 1913.37  5643.1 1919.21
  5679.5 1922.84  5686.0 1924.47  5712.3 1927.97  5743.3 1932.92  5785.6 1936.07
#Mann=6,-1,0
  4792.5     0.1       0  4952.8    0.05       0  4971.6     0.1       0
  5012.7   0.035       0  5477.7    0.07       0  5712.3     0.1       0
Bank Sta=4952.8,4971.6
Exp/Cntr=0.3,0.1

Type RM Length L Ch R = 1,15695,448,448,448
BEGIN DESCRIPTION:
Honey Creek 29.0
END DESCRIPTION:
XS GIS Cut Line= 3
      1853525.02     13946674.99      1853325.00     13946725.00
      1852775.01     13947324.99
#Sta/Elev= 30
  4775.1 1923.19  4834.4 1912.05  4839.5 1912.38  4909.1 1895.94  4916.9 1892.18
  4922.0 1891.34  4929.7 1868.36  4940.0 1863.87  4950.4 1861.85  4963.2 1854.71
  4979.0 1853.58  4979.5 1853.08  4997.8 1853.58  5010.9 1853.75  5051.9 1853.71
  5073.5 1854.38  5087.6 1859.43  5101.8 1862.60  5214.7 1865.89  5253.9 1868.44
  5407.6 1880.80  5462.6 1887.86  5590.2 1910.35  5597.0 1910.48  5604.4 1913.55
  5625.3 1917.05  5696.3 1934.39  5724.6 1939.83  5759.8 1945.61  5795.2 1946.83
#Mann=7,-1,0
  4775.1     0.1       0  4979.0    0.05       0  4997.8     0.1       0
  5010.9    0.07       0  5051.9   0.035       0  5253.9    0.07       0
  5407.6     0.1       0
Bank Sta=4979,4997.8
Exp/Cntr=0.3,0.1

Type RM Length L Ch R = 1,15247,436,436,436
BEGIN DESCRIPTION:
Honey Creek 28.0
END DESCRIPTION:
XS GIS Cut Line= 3
      1853474.96     13946325.01      1853025.00     13946475.00
      1852625.01     13946575.00
#Sta/Elev= 30
  4517.2 1921.03  4559.3 1917.52  4580.4 1913.74  4728.0 1882.87  4754.3 1879.43
  4759.6 1877.39  4833.4 1869.37  4886.1 1867.47  4938.8 1863.02  4970.4 1854.30
  4971.6 1851.88  4972.1 1851.38  4990.4 1851.88  5008.8 1852.05  5087.7 1852.09
  5138.4 1856.89  5179.6 1856.98  5190.2 1855.43  5228.6 1854.48  5249.2 1860.18
  5256.9 1865.07  5269.8 1891.90  5290.4 1903.83  5311.0 1921.02  5331.7 1932.10
  5352.3 1948.82  5362.6 1953.79  5372.9 1963.50  5385.8 1966.08  5403.8 1972.43
#Mann=6,-1,0
  4517.2     0.1       0  4971.6    0.05       0  4990.4     0.1       0
  5008.8   0.035       0  5087.7    0.07       0  5190.2     0.1       0
Bank Sta=4971.6,4990.4
Exp/Cntr=0.3,0.1

Type RM Length L Ch R = 1,14811,548,548,548
BEGIN DESCRIPTION:
Honey Creek 27.0
END DESCRIPTION:
XS GIS Cut Line= 3
      1853324.99     13946275.00      1852725.00     13946225.00
      1852525.03     13946274.99
#Sta/Elev= 30
  4397.5 1895.15  4455.2 1880.88  4460.2 1880.65  4490.7 1873.48  4507.9 1870.34
  4548.0 1867.01  4638.3 1864.86  4696.0 1862.30  4821.5 1861.49  4859.1 1860.26
  4889.2 1858.13  4919.3 1850.92  4929.3 1849.59  4941.9 1849.62  4949.4 1847.99
  4980.1 1847.67  4980.6 1847.17  4998.9 1847.67  5017.6 1848.65  5030.5 1852.58
  5051.1 1908.66  5058.8 1921.54  5064.0 1917.48  5071.7 1925.46  5082.0 1950.58
  5092.3 1957.16  5100.1 1960.55  5113.0 1963.61  5174.8 1969.30  5205.7 1973.85
#Mann=4,-1,0
  4397.5     0.1       0  4490.7    0.07       0  4980.1    0.05       0
  4998.9     0.1       0
Bank Sta=4980.1,4998.9
Exp/Cntr=0.3,0.1

Type RM Length L Ch R = 1,14263,203,203,203
BEGIN DESCRIPTION:
Honey Creek 26.0
END DESCRIPTION:
XS GIS Cut Line= 3
      1853475.04     13946025.02      1852875.00     13945775.00
      1852525.02     13945475.02
#Sta/Elev= 30
  4335.2 1920.24  4367.7 1917.34  4426.8 1905.36  4450.6 1897.84  4479.9 1891.82
  4527.5 1875.03  4579.4 1865.01  4769.1 1857.17  4855.2 1858.24  4895.5 1856.63
  4931.1 1855.76  4941.4 1854.00  4952.7 1849.27  4970.6 1847.77  5060.0 1847.54
  5060.5 1847.04  5080.6 1847.54  5121.5 1849.98  5131.9 1851.00  5169.6 1856.44
  5205.3 1867.04  5254.7 1887.15  5283.2 1893.02  5289.8 1895.77  5311.8 1899.00
  5332.6 1906.58  5340.3 1905.61  5361.2 1908.50  5396.3 1917.55  5446.2 1924.55
#Mann=7,-1,0
  4335.2     0.1       0  4579.4    0.07       0  4895.5     0.1       0
  5060.0    0.05       0  5080.6     0.1       0  5121.5   0.035       0
  5131.9     0.1       0
Bank Sta=5060,5080.6
Exp/Cntr=0.3,0.1

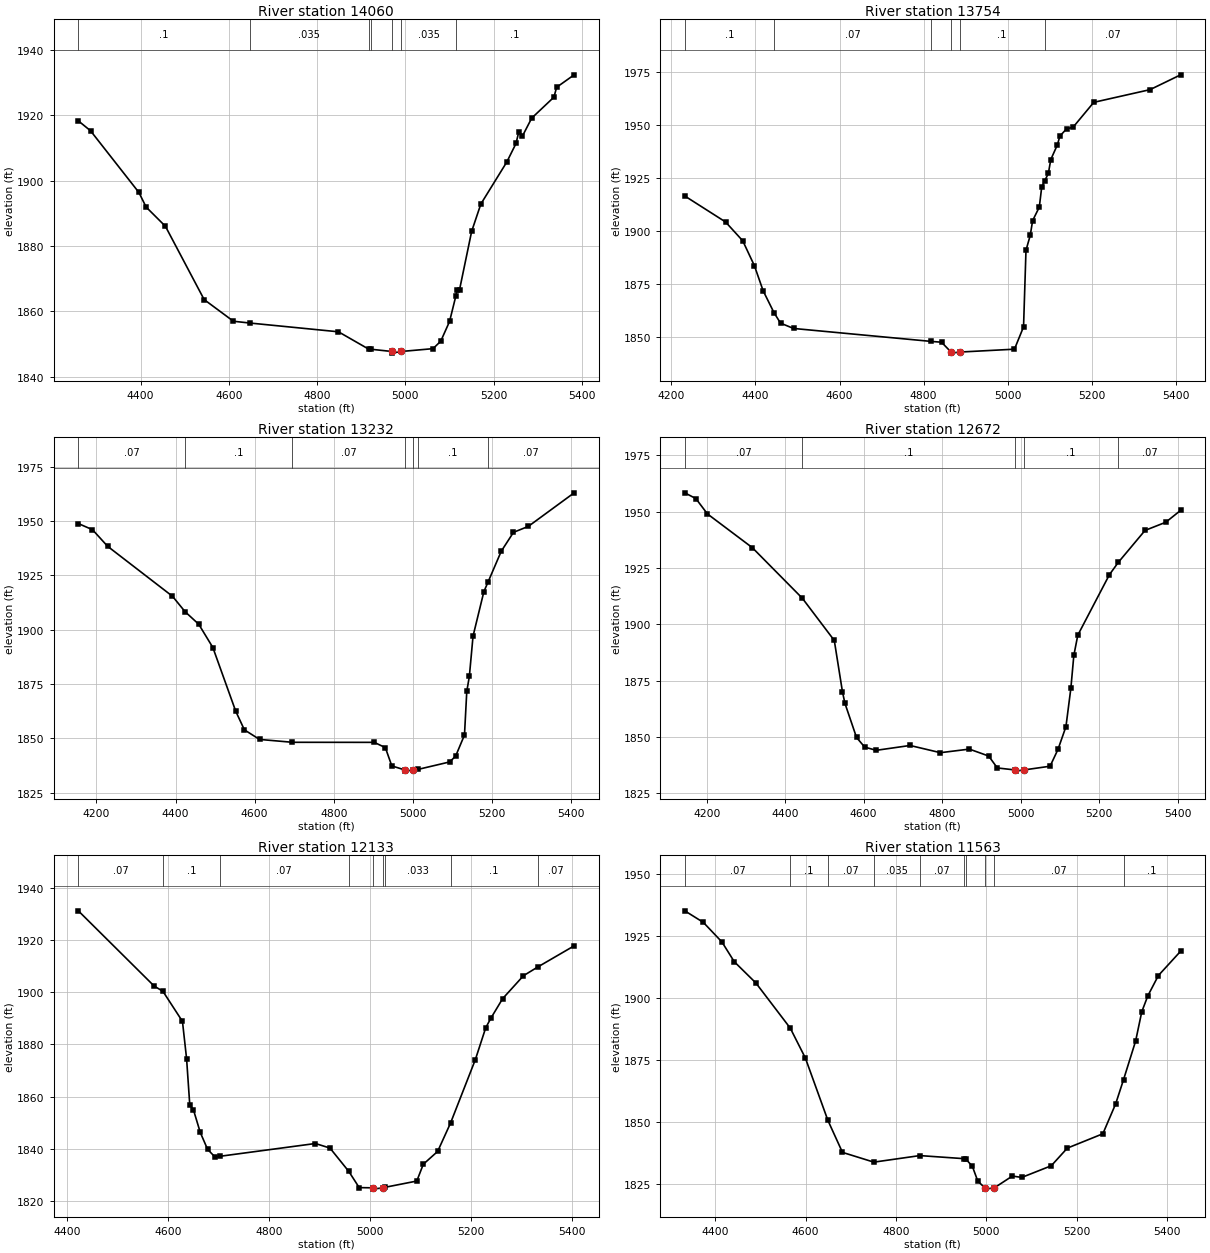
Type RM Length L Ch R = 1,14060,306,306,306
BEGIN DESCRIPTION:
Honey Creek 25.1
END DESCRIPTION:
XS GIS Cut Line= 4
      1853544.95     13945882.66      1853013.26     13945598.37
      1852756.10     13945587.52      1852542.35     13945433.44
#Sta/Elev= 30
  4258.8 1918.30  4286.4 1915.27  4396.1 1896.37  4412.4 1891.91  4456.2 1886.01
  4544.0 1863.57  4610.3 1856.94  4647.1 1856.40  4848.4 1853.71  4917.3 1848.37
  4922.6 1848.36  4969.8 1847.68  4970.3 1847.18  4990.4 1847.68  5062.7 1848.55
  5080.2 1850.83  5100.2 1856.88  5114.4 1864.65  5117.2 1866.65  5122.9 1866.65
  5150.2 1884.43  5171.1 1892.83  5229.9 1905.69  5250.8 1911.37  5257.0 1914.87
  5265.5 1913.67  5286.4 1919.14  5336.7 1925.55  5342.9 1928.58  5382.6 1932.39
#Mann=7,-1,0
  4258.8     0.1       0  4647.1   0.035       0  4917.3     0.1       0
  4922.6   0.035       0  4969.8   0.035       0  4990.4   0.035       0
  5114.4     0.1       0
Bank Sta=4969.8,4990.4
Exp/Cntr=0.3,0.1

Type RM Length L Ch R = 1,13754,522,522,522
BEGIN DESCRIPTION:
Honey Creek 25.0
END DESCRIPTION:
XS GIS Cut Line= 3
      1853675.00     13945525.00      1852925.00     13945325.00
      1852725.01     13944975.02
#Sta/Elev= 30
  4232.0 1916.44  4329.0 1904.18  4369.8 1895.30  4397.6 1883.53  4418.3 1871.74
  4444.1 1861.42  4459.7 1856.46  4490.7 1853.95  4817.9 1847.84  4842.6 1847.46
  4865.3 1842.81  4865.8 1842.31  4885.9 1842.81  5016.1 1844.17  5037.7 1854.71
  5043.5 1890.83  5053.6 1897.85  5059.3 1904.82  5075.2 1911.23  5080.9 1920.68
  5087.8 1923.54  5096.7 1927.09  5102.5 1933.63  5118.3 1940.65  5124.1 1944.72
  5139.9 1948.09  5155.8 1948.96  5204.7 1960.63  5338.6 1966.62  5411.3 1973.61
#Mann=6,-1,0
  4232.0     0.1       0  4444.1    0.07       0  4817.9     0.1       0
  4865.3    0.05       0  4885.9     0.1       0  5087.8    0.07       0
Bank Sta=4865.3,4885.9
Exp/Cntr=0.3,0.1

Type RM Length L Ch R = 1,13232,560,560,560
BEGIN DESCRIPTION:
Honey Creek 24.0
END DESCRIPTION:
XS GIS Cut Line= 3
      1854025.04     13945425.02      1853275.00     13945025.00
      1852924.97     13944824.98
#Sta/Elev= 30
  4154.3 1948.84  4190.1 1946.01  4228.4 1938.36  4392.3 1915.37  4424.1 1908.28
  4458.6 1902.51  4494.3 1891.80  4552.1 1862.48  4574.0 1853.91  4612.3 1849.50
  4695.4 1848.18  4902.3 1848.15  4930.3 1845.72  4946.6 1837.32  4980.2 1835.41
  4980.7 1834.91  5000.8 1835.41  5013.4 1835.73  5092.9 1839.14  5108.0 1841.84
  5130.3 1851.54  5136.1 1871.63  5142.6 1878.49  5151.9 1897.01  5179.3 1917.50
  5190.4 1922.16  5223.2 1936.09  5254.1 1944.80  5291.6 1947.53  5407.5 1962.98
#Mann=7,-1,0
  4154.3    0.07       0  4424.1     0.1       0  4695.4    0.07       0
  4980.2    0.05       0  5000.8    0.07       0  5013.4     0.1       0
  5190.4    0.07       0
Bank Sta=4980.2,5000.8
Exp/Cntr=0.3,0.1

Type RM Length L Ch R = 1,12672,539,539,539
BEGIN DESCRIPTION:
Honey Creek 23.0
END DESCRIPTION:
XS GIS Cut Line= 3
      1854324.97     13945124.98      1853625.00     13944625.00
      1853225.01     13944575.00
#Sta/Elev= 30
  4144.3 1958.31  4172.5 1955.76  4202.0 1948.95  4316.3 1933.99  4443.7 1911.56
  4525.2 1892.81  4546.1 1869.94  4552.3 1864.93  4581.8 1849.79  4602.6 1845.51
  4632.1 1844.08  4718.2 1846.23  4795.6 1843.03  4869.3 1844.62  4918.5 1841.55
  4940.6 1836.26  4986.8 1835.35  4987.3 1834.85  5007.5 1835.35  5075.0 1837.03
  5095.2 1844.52  5115.4 1854.58  5127.9 1871.55  5135.5 1886.16  5145.6 1895.16
  5226.2 1922.01  5248.8 1927.46  5316.9 1941.63  5369.8 1945.26  5407.6 1950.53
#Mann=5,-1,0
  4144.3    0.07       0  4443.7     0.1       0  4986.8    0.05       0
  5007.5     0.1       0  5248.8    0.07       0
Bank Sta=4986.8,5007.5
Exp/Cntr=0.3,0.1

Type RM Length L Ch R = 1,12133,570,570,570
BEGIN DESCRIPTION:
Honey Creek 22.0
END DESCRIPTION:
XS GIS Cut Line= 3
      1854375.02     13944775.03      1854025.00     13944325.00
      1853625.03     13944225.01
#Sta/Elev= 30
  4422.5 1931.25  4572.7 1902.40  4590.1 1900.37  4628.8 1888.84  4637.0 1874.51
  4643.3 1856.79  4650.6 1854.90  4664.1 1846.23  4678.6 1839.75  4693.1 1836.85
  4702.8 1837.08  4892.2 1841.99  4921.1 1840.24  4958.4 1831.28  4979.0 1825.07
  5005.5 1824.99  5006.0 1824.49  5026.2 1824.99  5030.9 1825.22  5093.1 1827.59
  5106.0 1834.04  5134.4 1838.95  5160.0 1849.85  5209.1 1874.16  5229.7 1886.40
  5240.0 1890.10  5263.2 1897.56  5304.4 1906.35  5333.0 1909.73  5404.9 1917.82
#Mann=9,-1,0
  4422.5    0.07       0  4590.1     0.1       0  4702.8    0.07       0
  4958.4     0.1       0  5005.5    0.05       0  5026.2     0.1       0
  5030.9   0.033       0  5160.0     0.1       0  5333.0    0.07       0
Bank Sta=5005.5,5026.2
Exp/Cntr=0.3,0.1

Type RM Length L Ch R = 1,11563,539,539,539
BEGIN DESCRIPTION:
Honey Creek 21.0
END DESCRIPTION:
XS GIS Cut Line= 3
      1854625.00     13944674.99      1854475.00     13944025.00
      1854224.99     13943674.99
#Sta/Elev= 30
  4332.7 1935.11  4373.7 1930.46  4414.8 1922.59  4442.2 1914.63  4490.1 1906.05
  4566.1 1887.89  4599.5 1875.86  4649.4 1850.74  4681.6 1837.88  4751.1 1833.95
  4852.8 1836.59  4950.7 1835.35  4954.4 1835.22  4969.0 1832.29  4981.0 1826.34
  4996.7 1823.59  4997.2 1823.09  5017.5 1823.59  5057.5 1828.35  5078.4 1827.80
  5143.6 1832.49  5179.2 1839.60  5257.8 1845.37  5286.1 1857.39  5303.5 1867.11
  5330.3 1882.69  5343.9 1894.47  5357.4 1900.92  5380.7 1909.07  5429.9 1918.85
#Mann=10,-1,0
  4332.7    0.07       0  4566.1     0.1       0  4649.4    0.07       0
  4751.1   0.035       0  4852.8    0.07       0  4950.7     0.1       0
  4954.4    0.07       0  4996.7    0.05       0  5017.5    0.07       0
  5303.5     0.1       0
Bank Sta=4996.7,5017.5
Exp/Cntr=0.3,0.1