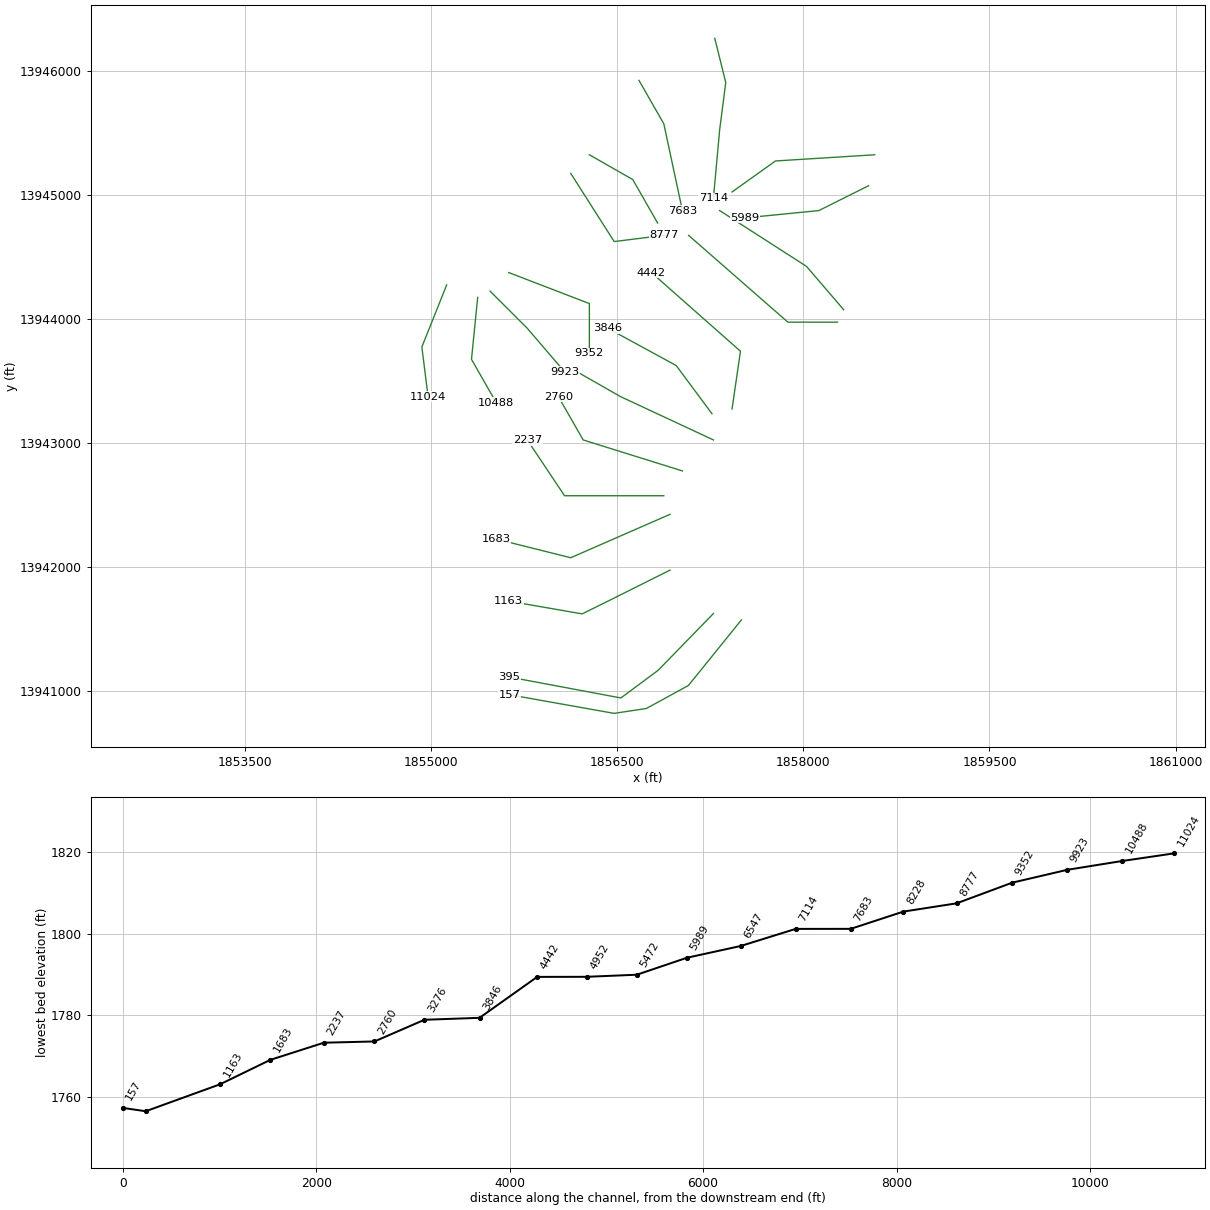
HEC-RAS study Honey Creek.prj: Honey Creek Base Level Engineering

--- Honey Creek.g01 (geometry) --- (continued)

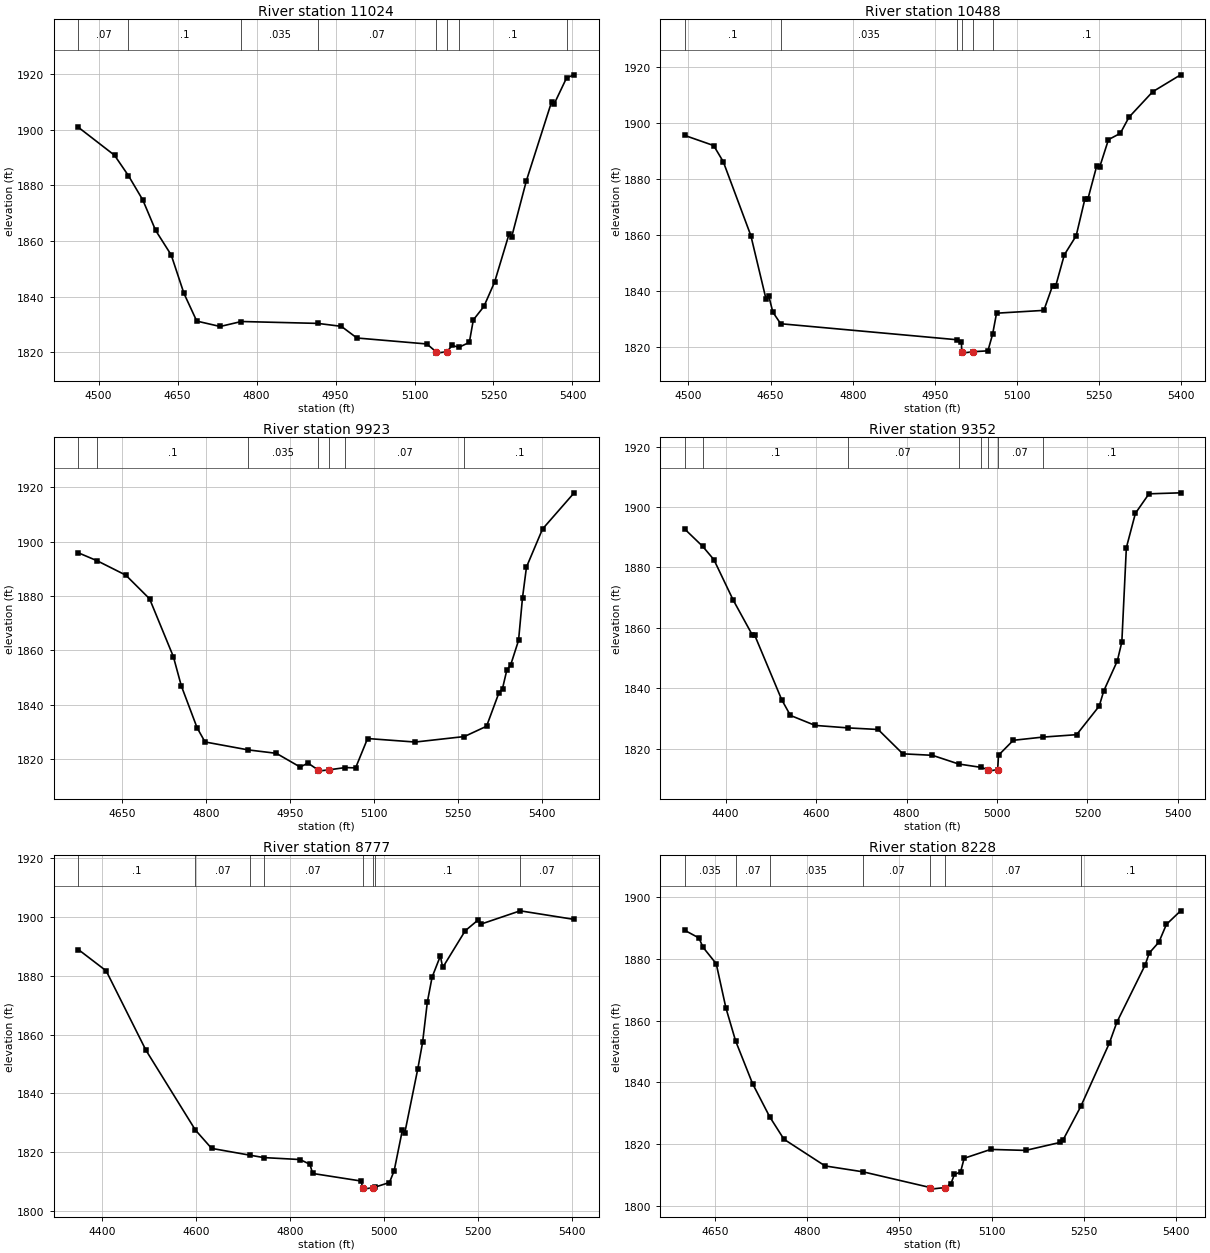
Type RM Length L Ch R = 1,11024,536,536,536
BEGIN DESCRIPTION:
Honey Creek 20.0
END DESCRIPTION:
XS GIS Cut Line= 3
      1855125.01     13944275.02      1854925.00     13943775.00
      1854975.01     13943374.95
#Sta/Elev= 30
  4461.5 1900.93  4530.2 1890.87  4556.6 1883.55  4584.0 1874.77  4608.3 1863.85
  4637.9 1855.01  4662.1 1841.19  4686.4 1831.24  4730.8 1829.30  4771.2 1831.09
  4916.3 1830.41  4961.0 1829.35  4990.6 1825.16  5123.5 1823.01  5140.8 1820.22
  5141.3 1819.72  5161.6 1820.22  5171.4 1822.48  5184.4 1821.82  5204.1 1823.58
  5211.7 1831.67  5231.8 1836.51  5252.0 1845.22  5279.7 1862.63  5284.7 1861.65
  5312.5 1881.74  5360.3 1910.06  5365.4 1909.38  5388.9 1918.73  5403.2 1919.79
#Mann=8,-1,0
  4461.5    0.07       0  4556.6     0.1       0  4771.2   0.035       0
  4916.3    0.07       0  5140.8    0.05       0  5161.6    0.07       0
  5184.4     0.1       0  5388.9    0.07       0
Bank Sta=5140.8,5161.6
Exp/Cntr=0.3,0.1

Type RM Length L Ch R = 1,10488,565,565,565
BEGIN DESCRIPTION:
Honey Creek 19.0
END DESCRIPTION:
XS GIS Cut Line= 3
      1855375.00     13944174.96      1855325.00     13943675.00
      1855525.01     13943324.97
#Sta/Elev= 30
  4493.3 1895.69  4546.0 1892.08  4563.6 1886.29  4613.9 1859.90  4641.5 1837.30
  4646.5 1838.40  4654.1 1832.51  4668.4 1828.36  4989.7 1822.65  4998.6 1821.93
  4999.0 1818.35  4999.5 1817.85  5019.8 1818.35  5046.9 1818.67  5055.4 1824.53
  5062.7 1832.13  5149.1 1833.14  5164.9 1841.89  5170.7 1841.85  5186.5 1853.01
  5208.1 1859.80  5223.9 1872.85  5229.7 1873.08  5245.5 1884.66  5251.3 1884.54
  5267.1 1894.20  5288.7 1896.44  5304.6 1902.22  5347.8 1911.31  5398.9 1917.37
#Mann=6,-1,0
  4493.3     0.1       0  4668.4   0.035       0  4989.7    0.07       0
  4999.0    0.05       0  5019.8    0.07       0  5055.4     0.1       0
Bank Sta=4999,5019.8
Exp/Cntr=0.3,0.1

Type RM Length L Ch R = 1,9923,571,571,571
BEGIN DESCRIPTION:
Honey Creek 18.0
END DESCRIPTION:
XS GIS Cut Line= 3
      1855475.03     13944224.97      1855775.00     13943925.00
      1856075.00     13943575.00
#Sta/Elev= 30
  4571.8 1895.87  4605.7 1892.92  4656.6 1887.66  4699.0 1878.98  4741.5 1857.72
  4755.6 1847.04  4783.9 1831.58  4798.0 1826.41  4875.2 1823.49  4925.3 1822.24
  4967.7 1817.22  4981.9 1818.64  4999.3 1816.20  4999.8 1815.70  5020.2 1816.20
  5048.4 1817.01  5066.8 1816.89  5088.2 1827.67  5173.3 1826.38  5261.0 1828.40
  5300.6 1832.18  5322.6 1844.40  5329.1 1846.04  5336.8 1852.82  5343.4 1854.54
  5357.7 1863.69  5364.8 1879.43  5371.9 1890.66  5400.5 1904.60  5457.0 1917.90
#Mann=7,-1,0
  4571.8    0.07       0  4605.7     0.1       0  4875.2   0.035       0
  4999.3   0.035       0  5020.2   0.035       0  5048.4    0.07       0
  5261.0     0.1       0
Bank Sta=4999.3,5020.2
Exp/Cntr=0.3,0.1

Type RM Length L Ch R = 1,9352,575,575,575
BEGIN DESCRIPTION:
Honey Creek 17.0
END DESCRIPTION:
XS GIS Cut Line= 3
      1855625.03     13944374.99      1856275.00     13944125.00
      1856275.00     13943724.99
#Sta/Elev= 30
  4309.6 1892.66  4349.2 1886.95  4373.9 1882.57  4416.7 1869.15  4458.5 1857.74
  4463.9 1857.64  4523.9 1836.18  4543.1 1830.98  4597.8 1827.67  4670.2 1826.85
  4737.1 1826.32  4791.7 1818.26  4857.1 1817.77  4915.2 1814.89  4964.4 1813.78
  4980.5 1813.03  4981.0 1812.53  5001.4 1813.03  5003.3 1817.80  5036.0 1822.74
  5100.6 1823.79  5176.0 1824.60  5226.0 1834.07  5236.0 1839.09  5266.0 1849.02
  5276.0 1855.29  5286.0 1886.52  5306.0 1897.90  5336.0 1904.36  5406.0 1904.69
#Mann=8,-1,0
  4309.6    0.07       0  4349.2     0.1       0  4670.2    0.07       0
  4915.2     0.1       0  4964.4    0.07       0  4980.5    0.05       0
  5001.4    0.07       0  5100.6     0.1       0
Bank Sta=4980.5,5001.4
Exp/Cntr=0.3,0.1

Type RM Length L Ch R = 1,8777,549,549,549
BEGIN DESCRIPTION:
Honey Creek 16.0
END DESCRIPTION:
XS GIS Cut Line= 3
      1856125.02     13945174.98      1856475.00     13944625.00
      1856875.00     13944675.00
#Sta/Elev= 30
  4349.3 1888.98  4408.5 1881.74  4493.2 1854.71  4598.4 1827.56  4632.9 1821.32
  4714.0 1819.02  4744.1 1818.19  4820.9 1817.53  4842.0 1815.92  4847.9 1812.79
  4951.2 1810.21  4954.1 1807.96  4954.6 1807.46  4977.2 1807.96  4981.3 1808.18
  5011.3 1809.71  5021.3 1813.71  5039.0 1827.72  5044.0 1826.68  5071.7 1848.47
  5081.8 1857.39  5091.9 1871.10  5102.0 1879.57  5119.6 1886.78  5124.6 1882.87
  5172.5 1895.37  5200.2 1899.07  5205.3 1897.59  5289.4 1902.15  5404.3 1899.23
#Mann=8,-1,0
  4349.3     0.1       0  4598.4    0.07       0  4714.0   0.035       0
  4744.1    0.07       0  4954.1    0.05       0  4977.2    0.07       0
  4981.3     0.1       0  5289.4    0.07       0
Bank Sta=4954.1,4977.2
Exp/Cntr=0.3,0.1

Type RM Length L Ch R = 1,8228,545,545,545
BEGIN DESCRIPTION:
Honey Creek 15.0
END DESCRIPTION:
XS GIS Cut Line= 3
      1856275.04     13945324.98      1856625.00     13945125.00
      1856825.01     13944774.98
#Sta/Elev= 30
  4601.1 1889.24  4624.1 1886.77  4630.6 1883.79  4652.2 1878.43  4668.0 1864.07
  4683.7 1853.44  4711.2 1839.64  4739.1 1828.87  4762.3 1821.60  4829.2 1812.95
  4890.7 1811.05  5000.5 1805.94  5001.0 1805.44  5023.6 1805.94  5033.7 1807.11
  5039.4 1810.20  5049.5 1810.99  5055.3 1815.43  5098.5 1818.30  5155.3 1817.98
  5210.8 1820.54  5216.5 1821.50  5245.0 1832.23  5291.4 1852.71  5303.6 1859.47
  5349.7 1878.06  5356.2 1881.87  5372.0 1885.43  5384.2 1891.17  5407.3 1895.56
#Mann=7,-1,0
  4601.1   0.035       0  4683.7    0.07       0  4739.1   0.035       0
  4890.7    0.07       0  5000.5    0.05       0  5023.6    0.07       0
  5245.0     0.1       0
Bank Sta=5000.5,5023.6
Exp/Cntr=0.3,0.1

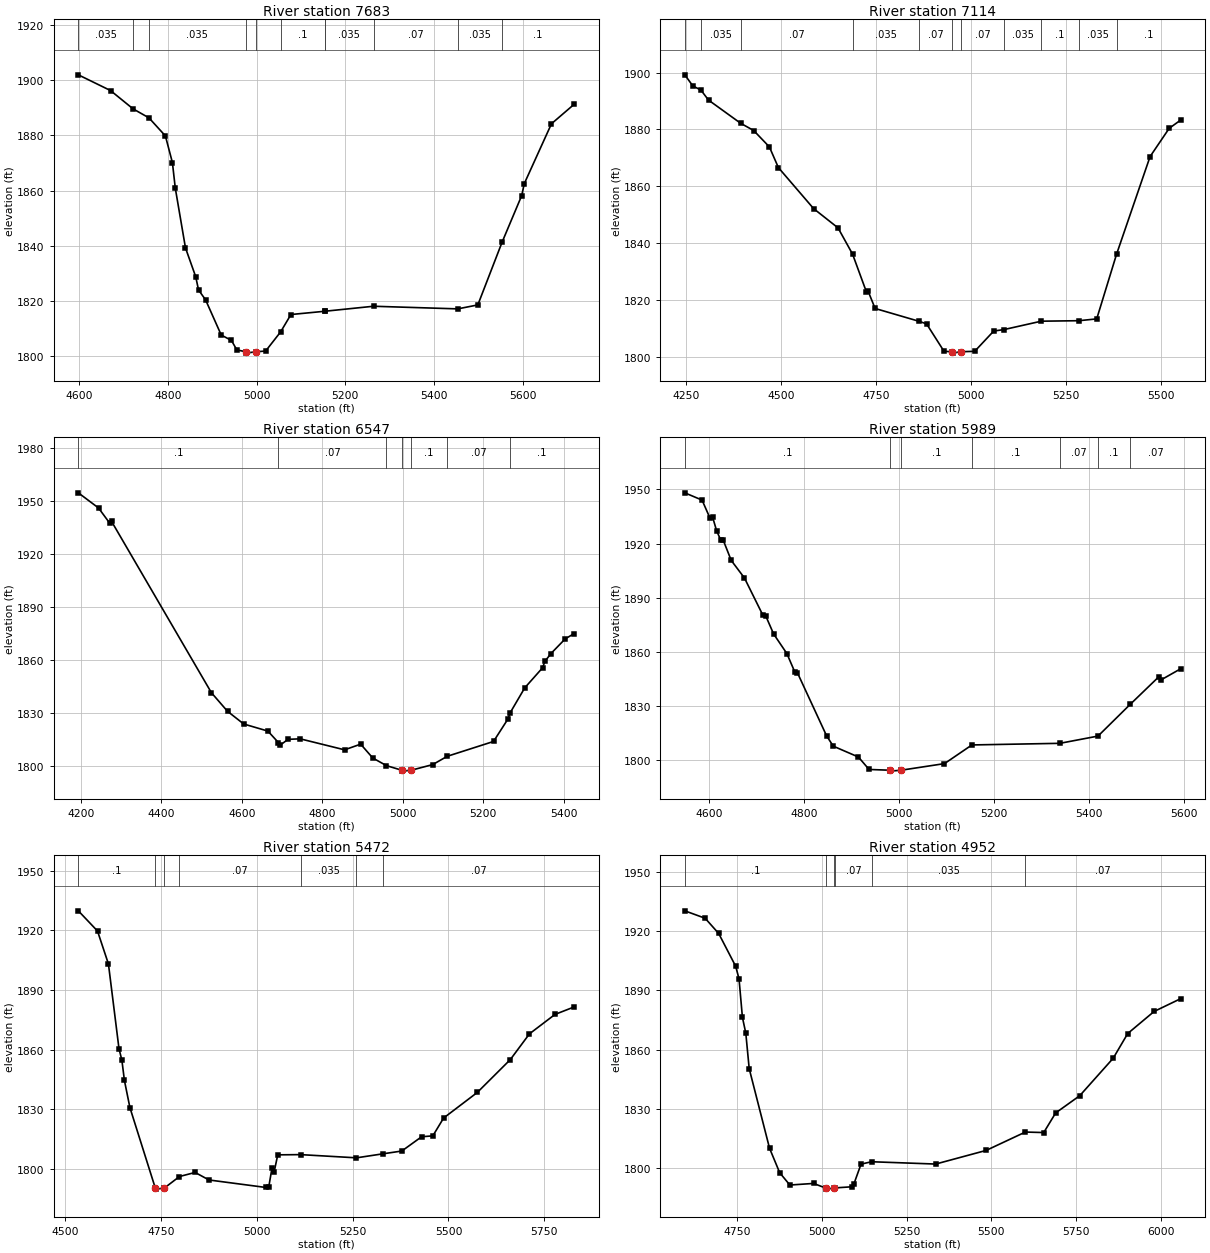
Type RM Length L Ch R = 1,7683,569,569,569
BEGIN DESCRIPTION:
Honey Creek 14.0
END DESCRIPTION:
XS GIS Cut Line= 3
      1856675.02     13945924.97      1856875.00     13945575.00
      1857025.01     13944874.97
#Sta/Elev= 30
  4597.4 1901.83  4670.1 1896.14  4720.8 1889.54  4756.8 1886.27  4793.9 1879.74
  4809.7 1870.11  4816.2 1860.88  4839.2 1839.26  4862.3 1828.83  4868.7 1824.04
  4884.6 1820.46  4919.9 1807.74  4942.9 1805.80  4955.1 1802.36  4975.3 1801.70
  4975.8 1801.20  4998.4 1801.70  5020.1 1801.95  5054.0 1808.89  5077.2 1815.16
  5153.9 1816.34  5154.2 1816.35  5263.6 1818.15  5453.6 1817.20  5499.0 1818.63
  5553.5 1841.22  5597.9 1858.12  5603.9 1862.51  5665.2 1884.14  5716.4 1891.18
#Mann=11,-1,0
  4597.4   0.035       0  4720.8    0.07       0  4756.8   0.035       0
  4975.3   0.035       0  4998.4   0.035       0  5054.0     0.1       0
  5153.9    0.07       0  5154.2   0.035       0  5263.6    0.07       0
  5453.6   0.035       0  5553.5     0.1       0
Bank Sta=4975.3,4998.4
Exp/Cntr=0.3,0.1

Type RM Length L Ch R = 1,7114,567,567,567
BEGIN DESCRIPTION:
Honey Creek 13.0
END DESCRIPTION:
XS GIS Cut Line= 4
      1857285.85     13946264.12      1857374.36     13945907.40
      1857325.00     13945525.00      1857275.00     13944974.98
#Sta/Elev= 30
  4246.6 1899.22  4267.7 1895.32  4289.1 1893.84  4309.0 1890.33  4393.6 1882.16
  4428.0 1879.60  4469.3 1873.83  4493.0 1866.54  4585.7 1852.10  4650.0 1845.31
  4688.3 1836.06  4724.4 1822.88  4729.4 1822.97  4747.6 1816.92  4862.8 1812.42
  4883.1 1811.50  4929.1 1801.82  4950.9 1801.69  4951.4 1801.19  4974.1 1801.69
  5009.8 1801.82  5060.0 1808.98  5086.1 1809.46  5185.1 1812.44  5284.2 1812.61
  5331.1 1813.25  5383.2 1835.98  5471.6 1870.43  5521.9 1880.38  5552.0 1883.27
#Mann=11,-1,0
  4246.6    0.07       0  4289.1   0.035       0  4393.6    0.07       0
  4688.3   0.035       0  4862.8    0.07       0  4950.9    0.05       0
  4974.1    0.07       0  5086.1   0.035       0  5185.1     0.1       0
  5284.2   0.035       0  5383.2     0.1       0
Bank Sta=4950.9,4974.1
Exp/Cntr=0.3,0.1

Type RM Length L Ch R = 1,6547,558,558,558
BEGIN DESCRIPTION:
Honey Creek 12.0
END DESCRIPTION:
XS GIS Cut Line= 3
      1858574.97     13945325.00      1857775.00     13945275.00
      1857425.04     13945025.03
#Sta/Elev= 30
  4194.1 1954.67  4244.2 1946.10  4271.7 1937.60  4276.7 1938.45  4524.7 1841.41
  4564.8 1830.87  4604.9 1823.70  4665.0 1819.68  4691.1 1813.17  4695.0 1811.66
  4715.1 1815.01  4745.1 1815.30  4855.4 1809.07  4895.4 1812.28  4925.5 1804.43
  4959.5 1800.11  4997.6 1797.50  4998.1 1797.00  5020.8 1797.50  5074.3 1800.70
  5110.5 1805.41  5225.4 1813.80  5261.1 1826.49  5266.9 1830.12  5302.9 1844.16
  5347.1 1855.51  5353.2 1859.22  5368.0 1863.60  5403.6 1871.96  5425.7 1874.92
#Mann=7,-1,0
  4194.1     0.1       0  4691.1    0.07       0  4959.5     0.1       0
  4997.6    0.05       0  5020.8     0.1       0  5110.5    0.07       0
  5266.9     0.1       0
Bank Sta=4997.6,5020.8
Exp/Cntr=0.3,0.1

Type RM Length L Ch R = 1,5989,517,517,517
BEGIN DESCRIPTION:
Honey Creek 11.0
END DESCRIPTION:
XS GIS Cut Line= 3
      1858525.04     13945075.02      1858125.00     13944875.00
      1857529.49     13944815.81
#Sta/Elev= 30
  4548.2 1948.12  4584.6 1944.10  4601.3 1934.14  4606.9 1934.63  4615.3 1927.12
  4623.7 1922.14  4629.3 1921.89  4646.1 1910.72  4674.0 1900.99  4713.2 1880.23
  4718.7 1880.13  4735.5 1870.03  4763.5 1859.15  4780.2 1848.96  4785.8 1848.50
  4847.3 1813.61  4861.3 1807.92  4914.4 1801.90  4936.8 1795.02  4981.0 1794.60
  4981.5 1794.10  5004.3 1794.60  5095.9 1798.26  5153.7 1808.59  5339.3 1809.49
  5419.7 1813.50  5487.6 1831.06  5547.4 1846.19  5552.4 1844.56  5593.9 1850.73
#Mann=7,-1,0
  4548.2     0.1       0  4981.0    0.05       0  5004.3     0.1       0
  5153.7     0.1       0  5339.3    0.07       0  5419.7     0.1       0
  5487.6    0.07       0
Bank Sta=4981,5004.3
Exp/Cntr=0.3,0.1

Type RM Length L Ch R = 1,5472,520,520,520
BEGIN DESCRIPTION:
Honey Creek 10.0
END DESCRIPTION:
XS GIS Cut Line= 3
      1858325.02     13944074.97      1858025.00     13944425.00
      1857324.98     13944875.01
#Sta/Elev= 30
  4534.7 1929.80  4584.7 1919.65  4613.2 1903.11  4640.7 1860.56  4648.3 1854.71
  4654.9 1844.55  4669.2 1830.94  4735.5 1790.44  4736.0 1789.94  4758.8 1790.44
  4798.5 1796.28  4839.3 1798.32  4875.5 1794.54  5024.4 1790.76  5031.4 1791.07
  5039.6 1800.33  5045.6 1798.78  5054.8 1807.17  5114.5 1807.28  5260.2 1805.67
  5330.0 1807.71  5378.4 1809.09  5430.0 1816.26  5459.3 1816.71  5487.4 1825.67
  5575.3 1838.53  5661.4 1855.04  5711.3 1867.98  5778.0 1877.75  5827.9 1881.50
#Mann=7,-1,0
  4534.7     0.1       0  4735.5    0.05       0  4758.8     0.1       0
  4798.5    0.07       0  5114.5   0.035       0  5260.2     0.1       0
  5330.0    0.07       0
Bank Sta=4735.5,4758.8
Exp/Cntr=0.3,0.1

Type RM Length L Ch R = 1,4952,510,510,510
BEGIN DESCRIPTION:
Honey Creek 9.0
END DESCRIPTION:
XS GIS Cut Line= 3
      1858274.97     13943975.00      1857875.00     13943975.00
      1857074.99     13944675.01
#Sta/Elev= 30
  4595.4 1930.18  4655.4 1926.43  4695.4 1918.72  4745.4 1902.18  4755.4 1895.81
  4765.4 1876.31  4775.4 1868.29  4785.4 1850.38  4845.4 1810.13  4875.4 1797.73
  4905.4 1791.50  4975.4 1792.31  5011.7 1789.93  5012.2 1789.43  5035.1 1789.93
  5039.3 1790.06  5087.9 1790.61  5094.6 1792.16  5115.4 1802.08  5146.8 1803.28
  5335.6 1802.11  5484.6 1809.01  5600.3 1818.30  5654.5 1818.04  5689.7 1827.97
  5760.8 1836.69  5859.5 1855.64  5902.3 1868.12  5980.1 1879.28  6058.4 1885.74
#Mann=6,-1,0
  4595.4     0.1       0  5011.7    0.05       0  5035.1     0.1       0
  5039.3    0.07       0  5146.8   0.035       0  5600.3    0.07       0
Bank Sta=5011.7,5035.1
Exp/Cntr=0.3,0.1

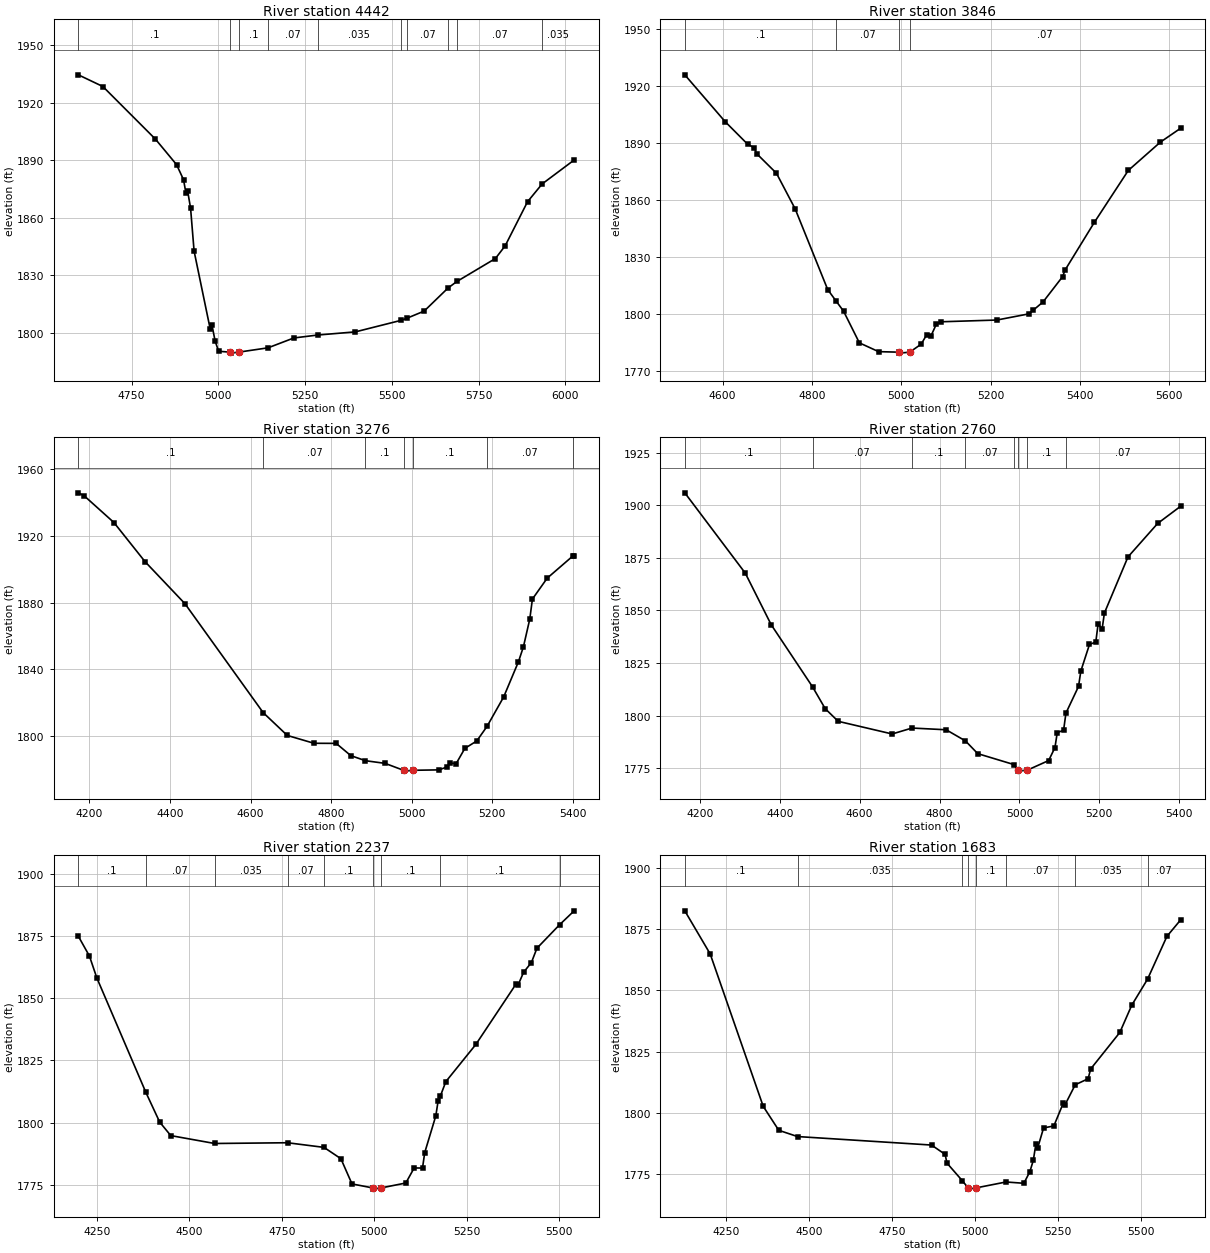
Type RM Length L Ch R = 1,4442,596,596,596
BEGIN DESCRIPTION:
Honey Creek 8.0
END DESCRIPTION:
XS GIS Cut Line= 3
      1857425.00     13943275.00      1857492.92     13943740.51
      1856774.97     13944375.03
#Sta/Elev= 30
  4596.6 1934.42  4667.3 1928.33  4818.9 1900.88  4879.6 1887.63  4899.8 1879.74
  4906.6 1872.75  4911.6 1873.79  4920.0 1864.96  4930.1 1842.60  4976.6 1801.94
  4981.6 1804.02  4990.7 1795.73  5000.8 1790.38  5034.8 1789.91  5035.3 1789.41
  5058.3 1789.91  5143.3 1792.18  5217.5 1797.31  5286.3 1798.84  5394.9 1800.49
  5526.7 1806.50  5544.0 1807.64  5593.1 1811.32  5662.1 1823.39  5687.3 1826.74
  5798.3 1838.70  5826.5 1845.35  5890.9 1868.30  5933.0 1877.57  6025.2 1890.04
#Mann=10,-1,0
  4596.6     0.1       0  5034.8    0.05       0  5058.3     0.1       0
  5143.3    0.07       0  5286.3   0.035       0  5526.7     0.1       0
  5544.0    0.07       0  5662.1     0.1       0  5687.3    0.07       0
  5933.0   0.035       0
Bank Sta=5034.8,5058.3
Exp/Cntr=0.3,0.1

Type RM Length L Ch R = 1,3846,570,570,570
BEGIN DESCRIPTION:
Honey Creek 7.0
END DESCRIPTION:
XS GIS Cut Line= 3
      1857263.16     13943236.45      1856975.00     13943625.00
      1856425.04     13943924.98
#Sta/Elev= 30
  4515.2 1925.69  4605.6 1901.06  4655.7 1889.25  4670.3 1887.37  4676.5 1884.16
  4720.4 1873.94  4762.4 1855.16  4835.2 1812.77  4854.4 1806.60  4870.6 1801.46
  4906.1 1784.76  4949.1 1780.14  4995.3 1779.86  4995.8 1779.36  5018.8 1779.86
  5044.5 1784.08  5056.4 1788.85  5066.8 1788.61  5078.7 1794.72  5088.6 1795.84
  5213.9 1796.76  5285.1 1799.98  5295.1 1801.88  5317.4 1806.28  5361.1 1819.57
  5366.8 1823.10  5432.3 1848.15  5508.2 1875.41  5579.9 1890.27  5625.4 1897.60
#Mann=4,-1,0
  4515.2     0.1       0  4854.4    0.07       0  4995.3    0.05       0
  5018.8    0.07       0
Bank Sta=4995.3,5018.8
Exp/Cntr=0.3,0.1

Type RM Length L Ch R = 1,3276,516,516,516
BEGIN DESCRIPTION:
Honey Creek 6.0
END DESCRIPTION:
XS GIS Cut Line= 3
      1857274.98     13943025.01      1856525.00     13943375.00
      1856175.04     13943574.98
#Sta/Elev= 30
  4172.6 1945.97  4186.8 1944.25  4260.9 1928.15  4338.1 1904.67  4437.4 1879.36
  4631.4 1814.00  4691.2 1800.31  4757.5 1795.60  4812.6 1795.54  4848.9 1788.19
  4885.3 1785.14  4934.0 1783.54  4979.8 1779.38  4980.3 1778.88  5003.4 1779.38
  5067.2 1779.63  5088.8 1781.44  5094.5 1783.72  5110.4 1783.38  5132.0 1792.54
  5161.5 1796.98  5187.0 1805.72  5228.4 1823.44  5265.1 1844.61  5277.4 1853.55
  5293.2 1870.25  5299.7 1882.20  5336.4 1894.74  5400.1 1908.05  5403.3 1908.13
#Mann=7,-1,0
  4172.6     0.1       0  4631.4    0.07       0  4885.3     0.1       0
  4979.8    0.05       0  5003.4     0.1       0  5187.0    0.07       0
  5400.1     0.1       0
Bank Sta=4979.8,5003.4
Exp/Cntr=0.3,0.1

Type RM Length L Ch R = 1,2760,523,523,523
BEGIN DESCRIPTION:
Honey Creek 5.0
END DESCRIPTION:
XS GIS Cut Line= 3
      1857025.00     13942775.00      1856225.00     13943025.00
      1856024.98     13943375.03
#Sta/Elev= 30
  4162.2 1905.98  4313.6 1867.77  4378.5 1843.22  4482.1 1813.64  4513.7 1803.28
  4546.2 1797.26  4681.3 1791.24  4731.1 1794.06  4816.5 1793.24  4864.8 1787.94
  4895.6 1781.88  4985.8 1776.70  4996.5 1774.06  4997.0 1773.56  5020.1 1774.06
  5073.1 1778.59  5088.9 1784.79  5094.6 1791.87  5110.5 1793.01  5116.4 1801.18
  5147.9 1813.86  5153.7 1821.17  5175.3 1833.84  5191.1 1834.96  5196.9 1843.59
  5206.9 1841.12  5212.7 1848.79  5271.7 1875.48  5345.9 1891.39  5403.5 1899.59
#Mann=8,-1,0
  4162.2     0.1       0  4482.1    0.07       0  4731.1     0.1       0
  4864.8    0.07       0  4985.8     0.1       0  4996.5    0.05       0
  5020.1     0.1       0  5116.4    0.07       0
Bank Sta=4996.5,5020.1
Exp/Cntr=0.3,0.1

Type RM Length L Ch R = 1,2237,554,554,554
BEGIN DESCRIPTION:
Honey Creek 4.0
END DESCRIPTION:
XS GIS Cut Line= 3
      1856874.95     13942575.00      1856075.00     13942575.00
      1855774.99     13943025.01
#Sta/Elev= 30
  4200.0 1874.83  4230.0 1866.87  4250.0 1858.10  4382.7 1812.08  4420.0 1800.18
  4450.0 1794.75  4568.5 1791.58  4765.7 1791.88  4864.3 1790.02  4910.0 1785.47
  4940.0 1775.34  4995.6 1773.75  4996.1 1773.25  5019.3 1773.75  5085.6 1775.71
  5108.1 1781.75  5130.7 1781.72  5136.7 1787.92  5166.7 1802.69  5172.7 1808.47
  5178.7 1810.51  5193.8 1816.43  5274.9 1831.35  5383.0 1855.48  5389.1 1855.21
  5404.1 1860.36  5425.1 1864.23  5440.1 1870.00  5501.3 1879.43  5540.8 1885.03
#Mann=9,-1,0
  4200.0     0.1       0  4382.7    0.07       0  4568.5   0.035       0
  4765.7    0.07       0  4864.3     0.1       0  4995.6    0.05       0
  5019.3     0.1       0  5178.7     0.1       0  5501.3    0.07       0
Bank Sta=4995.6,5019.3
Exp/Cntr=0.3,0.1

Type RM Length L Ch R = 1,1683,520,520,520
BEGIN DESCRIPTION:
Honey Creek 3.0
END DESCRIPTION:
XS GIS Cut Line= 3
      1856925.03     13942425.01      1856125.00     13942075.00
      1855525.01     13942225.00
#Sta/Elev= 30
  4126.7 1882.38  4203.1 1864.81  4362.6 1802.76  4409.4 1793.00  4465.8 1790.45
  4869.0 1786.99  4909.9 1783.19  4915.4 1779.64  4961.7 1772.46  4979.1 1769.54
  4979.6 1769.04  5002.8 1769.54  5093.2 1771.95  5146.8 1771.42  5164.9 1776.16
  5175.2 1780.78  5182.9 1787.38  5188.1 1785.71  5206.1 1793.96  5237.0 1794.77
  5265.4 1804.08  5270.5 1803.35  5301.3 1811.54  5340.1 1813.99  5347.8 1817.98
  5435.4 1832.83  5471.5 1843.98  5518.9 1854.55  5577.2 1871.99  5618.4 1878.69
#Mann=8,-1,0
  4126.7     0.1       0  4465.8   0.035       0  4961.7     0.1       0
  4979.1    0.05       0  5002.8     0.1       0  5093.2    0.07       0
  5301.3   0.035       0  5518.9    0.07       0
Bank Sta=4979.1,5002.8
Exp/Cntr=0.3,0.1

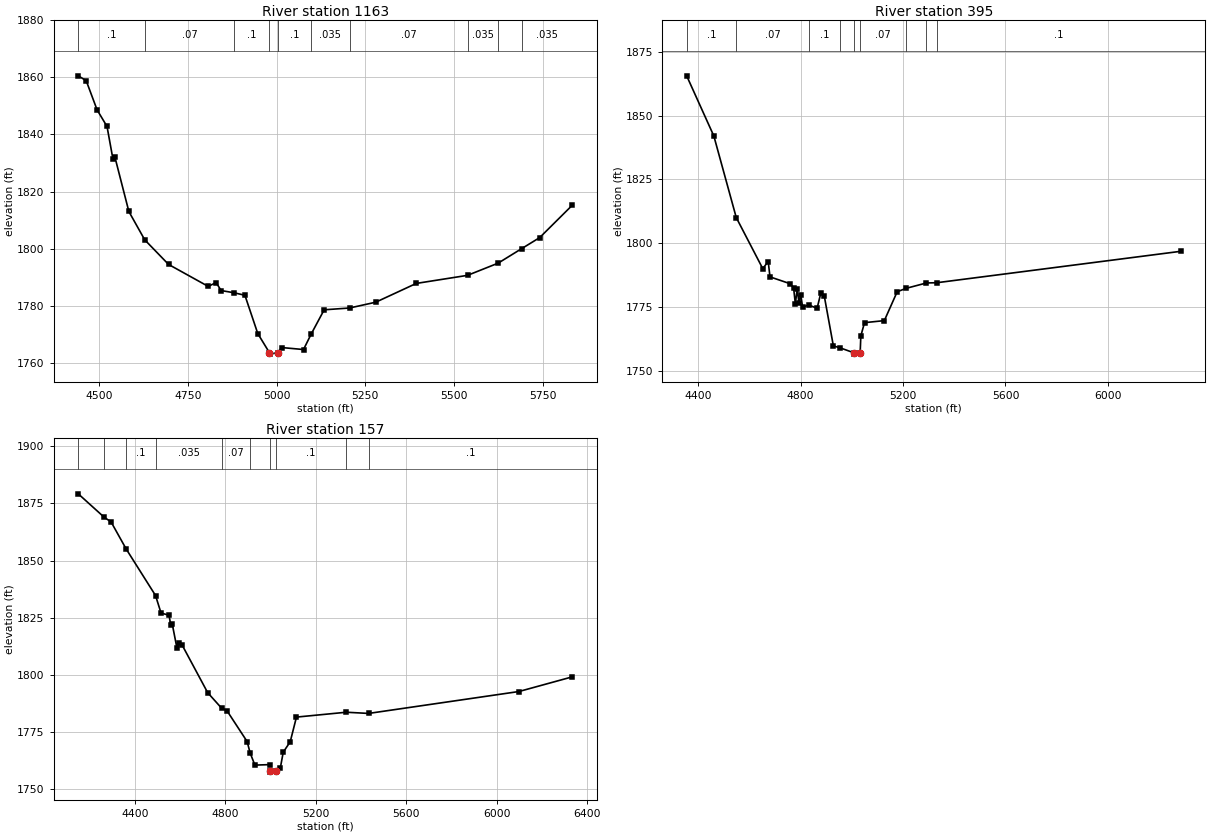
Type RM Length L Ch R = 1,1163,768,768,768
BEGIN DESCRIPTION:
Honey Creek 2.0
END DESCRIPTION:
XS GIS Cut Line= 4
      1856925.01     13941975.00      1856425.00     13941725.00
      1856217.11     13941622.02      1855625.02     13941725.00
#Sta/Elev= 30
  4441.0 1860.54  4463.4 1858.84  4494.1 1848.61  4522.1 1842.80  4538.8 1831.35
  4544.4 1832.02  4583.6 1813.01  4628.3 1803.09  4695.4 1794.47  4807.2 1786.77
  4829.5 1788.11  4843.5 1785.32  4880.3 1784.53  4910.6 1783.66  4946.9 1770.23
  4979.7 1763.54  4980.2 1763.04  5003.5 1763.54  5014.0 1765.35  5075.7 1764.65
  5097.1 1770.02  5133.9 1778.57  5205.4 1779.20  5279.2 1781.23  5393.4 1787.81
  5537.8 1790.64  5624.0 1794.91  5690.8 1800.03  5741.0 1803.85  5833.0 1815.21
#Mann=10,-1,0
  4441.0     0.1       0  4628.3    0.07       0  4880.3     0.1       0
  4979.7    0.05       0  5003.5     0.1       0  5097.1   0.035       0
  5205.4    0.07       0  5537.8   0.035       0  5624.0    0.07       0
  5690.8   0.035       0
Bank Sta=4979.7,5003.5
Exp/Cntr=0.3,0.1

Type RM Length L Ch R = 1,395,238,238,238
BEGIN DESCRIPTION:
Honey Creek 1.0
END DESCRIPTION:
XS GIS Cut Line= 4
      1857275.00     13941625.00      1856829.79     13941167.38
      1856529.22     13940943.90      1855629.14     13941112.79
#Sta/Elev= 30
  4355.4 1865.65  4461.5 1842.03  4549.0 1810.02  4652.4 1790.00  4673.7 1792.78
  4680.7 1786.75  4758.6 1784.09  4772.7 1782.55  4779.7 1776.16  4786.9 1782.02
  4793.8 1776.56  4801.0 1779.66  4808.0 1774.84  4831.9 1775.73  4864.6 1774.41
  4878.7 1780.23  4892.9 1779.09  4928.1 1759.66  4955.3 1758.87  5008.8 1756.93
  5009.3 1756.43  5032.7 1756.93  5035.4 1763.60  5049.7 1768.78  5127.1 1769.58
  5177.2 1780.90  5211.8 1782.24  5291.6 1784.36  5331.7 1784.45  6284.2 1796.78
#Mann=9,-1,0
  4355.4     0.1       0  4549.0    0.07       0  4831.9     0.1       0
  4955.3    0.07       0  5008.8    0.05       0  5032.7    0.07       0
  5211.8   0.035       0  5291.6    0.07       0  5331.7     0.1       0
Bank Sta=5008.8,5032.7
Exp/Cntr=0.3,0.1

Type RM Length L Ch R = 1,157,0,0,0
BEGIN DESCRIPTION:
Honey Creek 0.0
END DESCRIPTION:
XS GIS Cut Line= 5
      1857500.83     13941573.95      1857073.49     13941044.62
      1856734.57     13940859.09      1856474.68     13940819.62
      1855632.60     13940969.72
#Sta/Elev= 30
  4149.4 1879.23  4262.5 1869.11  4294.9 1866.86  4361.5 1855.03  4491.2 1834.66
  4515.6 1826.97  4550.8 1826.03  4558.8 1821.62  4565.2 1822.12  4586.0 1811.59
  4594.0 1813.93  4608.3 1813.05  4721.9 1792.07  4783.4 1785.28  4806.7 1784.23
  4896.2 1770.67  4909.7 1765.62  4930.6 1760.33  4999.0 1760.55  4999.1 1757.75
  4999.6 1757.25  5023.0 1757.75  5043.2 1759.12  5056.0 1765.99  5086.9 1770.57
  5114.4 1781.37  5334.8 1783.50  5433.4 1782.98  6098.2 1792.58  6334.3 1799.01
#Mann=10,-1,0
  4149.4    0.07       0  4262.5   0.035       0  4361.5     0.1       0
  4491.2   0.035       0  4783.4    0.07       0  4909.7     0.1       0
  4999.1    0.05       0  5023.0     0.1       0  5334.8    0.07       0
  5433.4     0.1       0
Bank Sta=4999.1,5023
Exp/Cntr=0.3,0.1

Chan Stop Cuts=-1