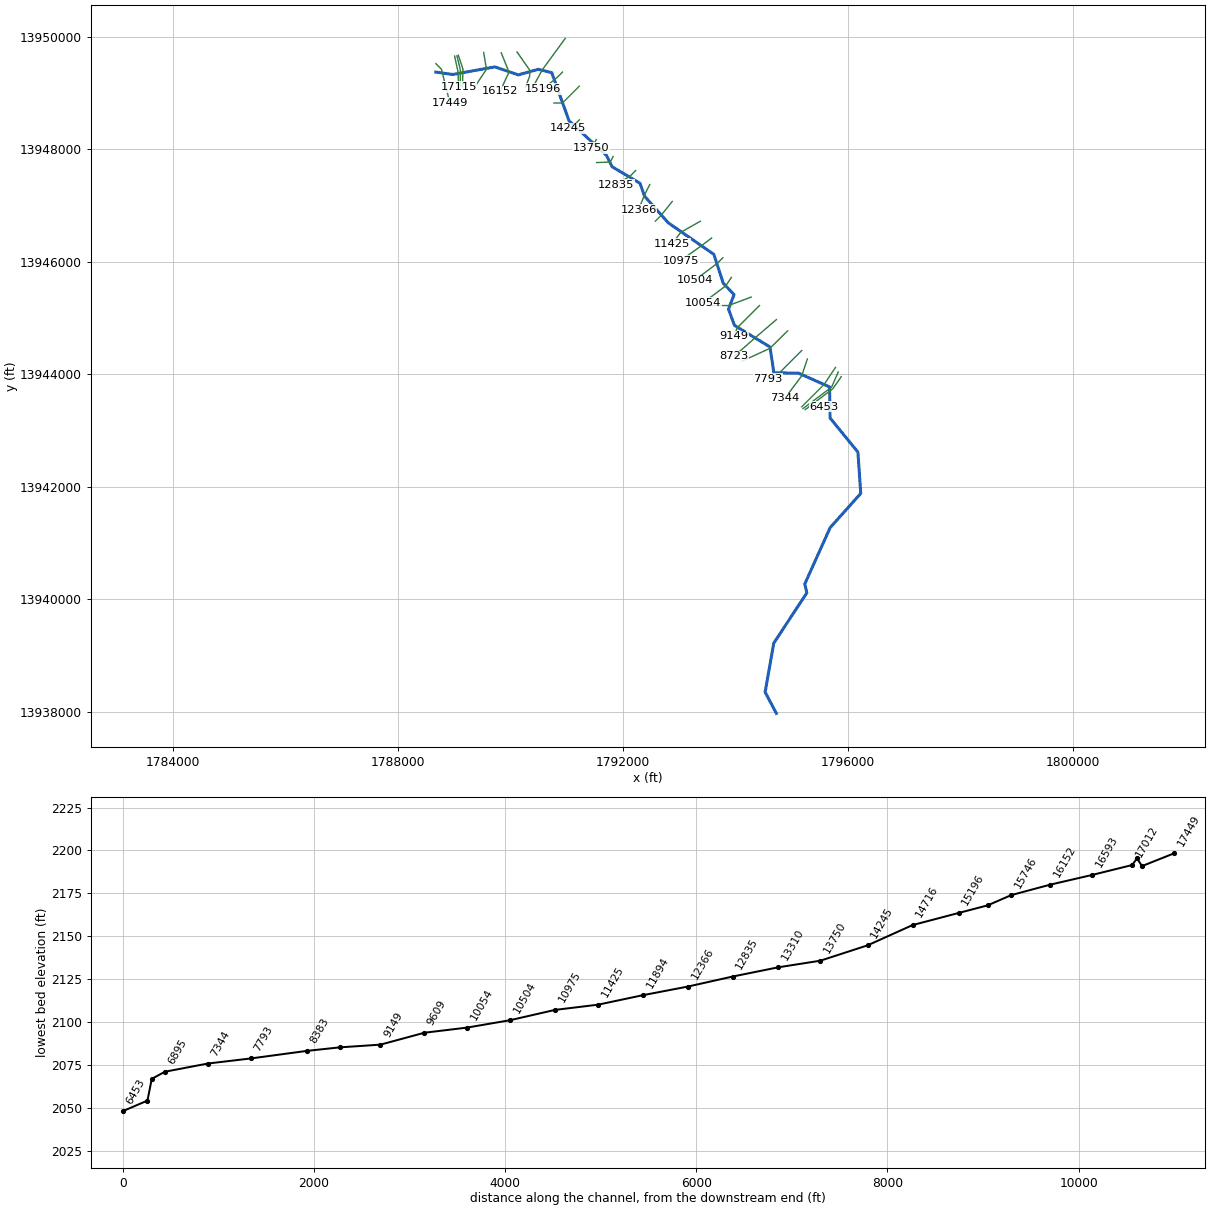
--- Indian Creek 01.prj (project) ---

Proj Title=Indian Creek 01 Base Level Engineering
Current Plan=p01
Default Exp/Contr=0.3,0.1
English Units
Geom File=g01
Flow File=f01
Plan File=p01
Y Axis Title=Elevation
X Axis Title(PF)=Main Channel Distance
X Axis Title(XS)=Station
BEGIN DESCRIPTION:
Indian Creek 01
END DESCRIPTION:
DSS Export Rating Curves= 0
DSS Export Rating Curve Sorted= 0
DSS Export Volume Flow Curves= 0
DXF OffsetX= 0
DXF OffsetY= 0
DXF ScaleX= 1
DXF ScaleY= 10

--- Indian Creek 01.p01 (plan) ---

Plan Title=Multiple Run
Short Identifier=Multiple
Geom File=g01
Flow File=f01
Subcritical Flow
K Sum by GR= 0
Std Step Tol= 0.01
Critical Tol= 0.01
Num of Std Step Trials= 20
Max Error Tol= 0.3
Flow Tol Ratio= 0.001
Split Flow NTrial= 30
Split Flow Tol= 0.02
Split Flow Ratio= 0.02
Log Output Level= 0
Friction Slope Method= 1
Unsteady Friction Slope Method= 2
Unsteady Bridges Friction Slope Method= 1
Parabolic Critical Depth
Global Vel Dist=  1 , 1 , 1
Global Log Level= 0
CheckData=True
Encroach Param= -1, 0, 0, 0
BEGIN DESCRIPTION:
Multiple Run
END DESCRIPTION:

--- Indian Creek 01.f01 (steady flow) ---

Flow Title=Multiple
Program Version=4.10
Number of Profiles= 7
Profile Names=10-year,25-year,50-year,1pct_min,100-year,1pct_plu,500-year
River Rch & RM=Indian Creek 01,Reach-1         ,17449
     307     482     635     407     811    1618    1303
River Rch & RM=Indian Creek 01,Reach-1         ,16593
    1164    2001    2803    1895    3781    7544    6807
River Rch & RM=Indian Creek 01,Reach-1         ,11894
    1827    3216    4574    3135    6255   12480   11580
River Rch & RM=Indian Creek 01,Reach-1         ,5342
    3746    6777    9812    6828   13624   27184   26016
River Rch & RM=Indian Creek 01,Reach-1         ,521
    3991    7238   10496    7315   14594   29120   27949
Boundary for River Rch & Prof#=Indian Creek 01,Reach-1         , 1
Up Type= 0
Dn Type= 3
Dn Slope=0.008
Boundary for River Rch & Prof#=Indian Creek 01,Reach-1         , 2
Up Type= 0
Dn Type= 3
Dn Slope=0.008
Boundary for River Rch & Prof#=Indian Creek 01,Reach-1         , 3
Up Type= 0
Dn Type= 3
Dn Slope=0.008
Boundary for River Rch & Prof#=Indian Creek 01,Reach-1         , 4
Up Type= 0
Dn Type= 3
Dn Slope=0.008
Boundary for River Rch & Prof#=Indian Creek 01,Reach-1         , 5
Up Type= 0
Dn Type= 3
Dn Slope=0.008
Boundary for River Rch & Prof#=Indian Creek 01,Reach-1         , 6
Up Type= 0
Dn Type= 3
Dn Slope=0.008
Boundary for River Rch & Prof#=Indian Creek 01,Reach-1         , 7
Up Type= 0
Dn Type= 3
Dn Slope=0.008
DSS Import GetInterval= 0
DSS Import GetPeak= 0
DSS Import FillOption= 0

--- Indian Creek 01.g01 (geometry) ---

Geom Title=Existing Conditions
Program Version=4.10

River Reach=Indian Creek 01 ,Reach-1
Reach XY= 30
        1788675.       13949375.      1788975.01     13949332.53
        1789725.     13949467.44      1790140.27     13949325.38
       1790497.7     13949425.12      1790734.71     13949364.25
      1791041.64     13948508.32      1791705.22     13947895.09
      1791807.87      13947691.3      1792301.99     13947398.47
      1792382.86     13947168.83      1792804.91     13946694.79
      1793614.25     13946134.71      1793780.52     13945622.57
      1793973.04     13945419.11       1793874.2     13945161.29
      1793980.36      13944872.3      1794611.46     13944488.54
      1794680.41     13944030.18      1795119.48     13944022.66
      1795669.64      13943777.7      1795678.75     13943226.55
        1796173.     13942619.63       1796223.8      13941885.5
      1795680.52     13941277.43      1795228.68     13940273.41
      1795265.87     13940118.26      1794678.54     13939223.53
      1794524.72     13938352.15        1794725.       13937975.

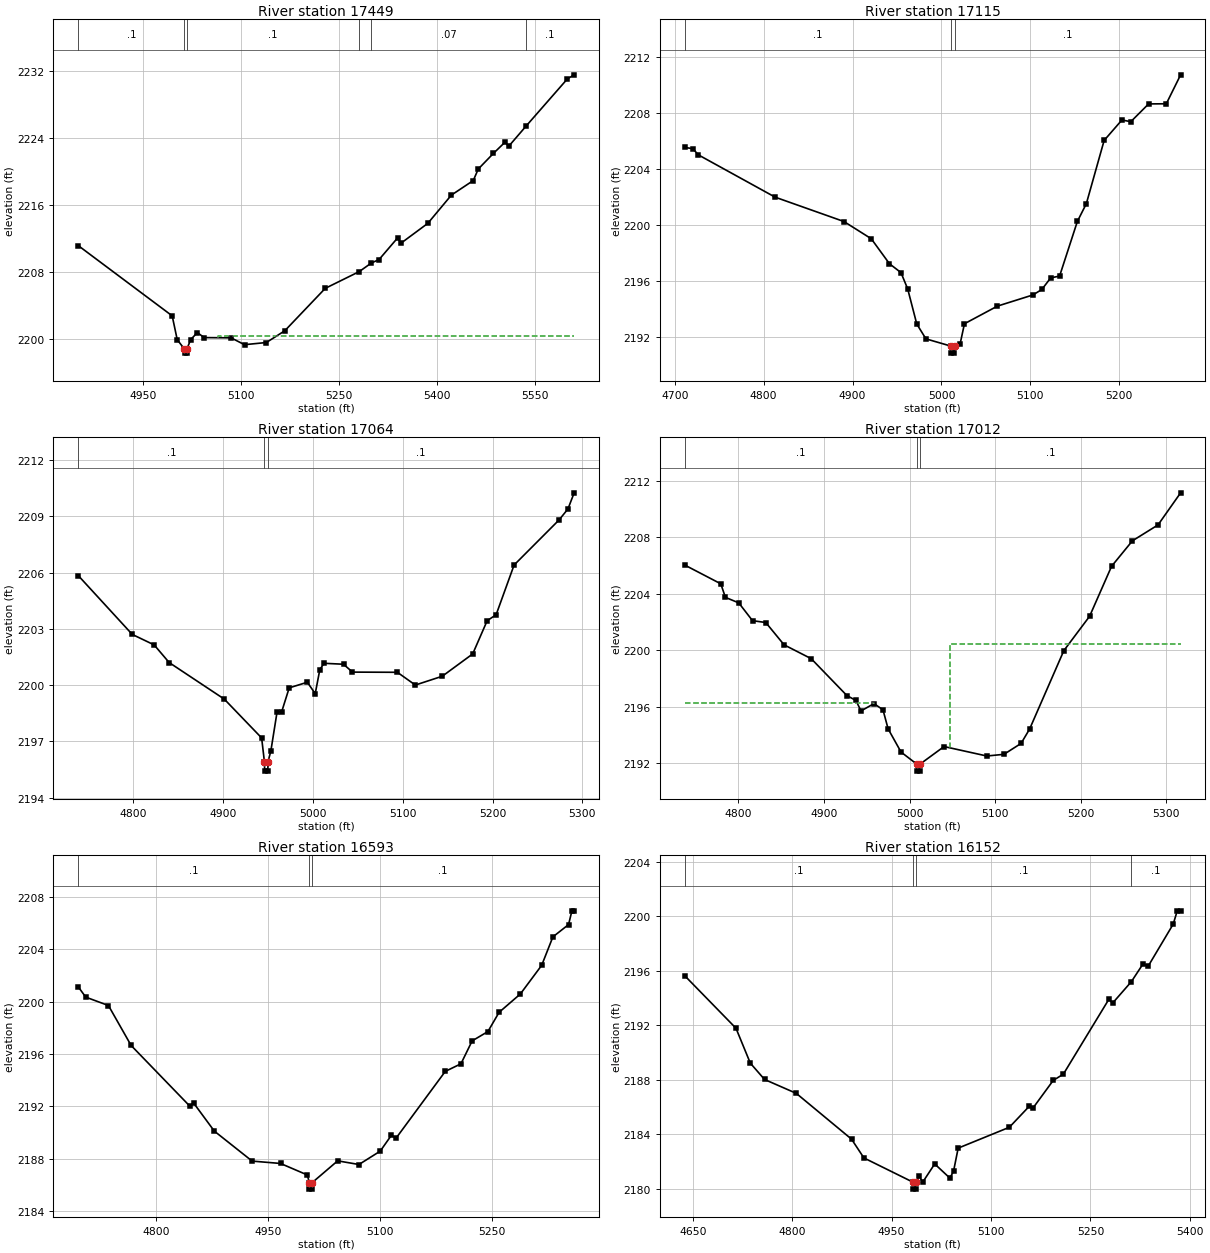
Type RM Length L Ch R = 1 ,17449   ,334,334,334
BEGIN DESCRIPTION:
Indian Creek 01 38.0
END DESCRIPTION:
XS GIS Cut Line= 3
      1788675.01     13949524.99        1788775.       13949425.
      1788925.01     13948824.98
#Sta/Elev= 30
  4850.7 2211.12  4994.7 2202.71  5002.4 2199.86  5013.3 2198.75  5013.6 2198.25
  5017.1 2198.25  5017.3 2198.75    5023 2199.87  5033.3 2200.71  5043.6 2200.11
  5084.9 2200.08  5105.5 2199.26    5139 2199.52  5167.3 2200.93  5229.2    2206
  5281.4 2208.01  5299.8 2209.03  5311.7 2209.45    5340 2212.03  5345.2  2211.4
  5386.4 2213.78  5422.5 2217.16    5456  2218.9  5463.7 2220.28  5486.9 2222.15
  5504.9 2223.51  5510.1 2222.98  5537.1 2225.43  5600.3 2231.07  5610.6 2231.55
#Mann= 6 ,-1 , 0
  4850.7      .1       0  5013.3     .05       0  5017.3      .1       0
  5281.4      .1       0  5299.8     .07       0  5537.1      .1       0
#XS Ineff= 2 , 0
                         5064.77         2200.34
Permanent Ineff=
       F       F
Bank Sta=5013.3,5017.3
XS Rating Curve= 0 ,0
Exp/Cntr=0.3,0.1

Type RM Length L Ch R = 1 ,17115   ,51,51,51
BEGIN DESCRIPTION:
Indian Creek 01 37.2
END DESCRIPTION:
XS GIS Cut Line= 3
      1789008.22     13949659.92      1789068.64     13949385.54
      1789080.48     13949109.05
#Sta/Elev= 30
  4711.2 2205.55  4720.4 2205.46  4726.5 2205.02    4813 2201.99  4890.3 2200.25
    4921 2199.02  4941.5 2197.23  4954.4  2196.6    4962 2195.43  4972.2 2192.92
  4982.5 2191.86  5010.7 2191.34    5011 2190.84  5014.5 2190.84  5014.7 2191.34
  5020.8 2191.46  5025.8 2192.94  5062.8  2194.2  5102.8    2195  5112.8 2195.39
  5122.8 2196.22  5132.8 2196.35  5152.8 2200.26  5162.9 2201.53  5182.9 2206.05
  5202.9 2207.51  5212.9 2207.39  5232.9 2208.66  5252.8 2208.67  5268.9 2210.74
#Mann= 3 ,-1 , 0
  4711.2      .1       0  5010.7     .05       0  5014.7      .1       0
Bank Sta=5010.7,5014.7
XS Rating Curve= 0 ,0
Exp/Cntr=0.3,0.1

Type RM Length L Ch R = 1 ,17064   ,52,52,52
BEGIN DESCRIPTION:
Mapping XS 206a5093
END DESCRIPTION:
XS GIS Cut Line= 4
      1789050.15     13949663.43      1789103.33     13949446.51
      1789111.41     13949393.24        1789109.     13949118.07
#Sta/Elev= 30
  4738.5 2205.84  4798.7  2202.7  4823.1 2202.14  4839.8  2201.2  4901.2 2199.25
  4942.8 2197.18  4945.9 2195.91  4946.2 2195.41  4949.7 2195.41  4949.9 2195.91
  4953.1 2196.49    4960 2198.57  4965.1 2198.57  4973.5 2199.85  4993.7 2200.15
  5002.5 2199.54  5007.6 2200.82  5012.3 2201.16    5034 2201.11    5044 2200.69
    5094 2200.68    5114    2200    5144 2200.47  5177.9 2201.66    5194 2203.43
    5204 2203.75    5224  2206.4    5274  2208.8    5284 2209.39  5290.9 2210.25
#Mann= 3 ,-1 , 0
  4738.5      .1       0  4945.9     .05       0  4949.9      .1       0
#XS Ineff= 1 ,-1
 5016.54  5290.9 2201.12
Permanent Ineff=
       F
Bank Sta=4945.9,4949.9
XS Rating Curve= 0 ,0
Exp/Cntr=0.3,0.1

Type RM Length L Ch R = 1 ,17012   ,419,419,419
BEGIN DESCRIPTION:
Indian Creek 01 37.0
END DESCRIPTION:
XS GIS Cut Line= 3
      1789074.99     13949675.03       1789156.5     13949429.01
      1789147.84     13949108.59
#Sta/Elev= 30
  4737.2 2206.05  4779.4 2204.72  4784.8 2203.76  4800.4 2203.37  4816.5 2202.11
    4832 2201.98  4853.4  2200.4  4885.1 2199.42  4926.8 2196.81  4937.4 2196.46
  4943.3 2195.72  4958.5 2196.24    4969  2195.8    4975 2194.45  4990.1 2192.81
  5008.4 2191.96  5008.6 2191.46  5012.1 2191.46  5012.4 2191.96  5040.4  2193.2
  5090.4 2192.53  5110.4 2192.65  5130.4 2193.42  5140.4 2194.44  5180.4 2199.99
  5210.5 2202.42  5236.2 2205.96  5260.5 2207.76  5290.5 2208.89  5316.9 2211.16
#Mann= 3 ,-1 , 0
  4737.2      .1       0  5008.4     .05       0  5012.4      .1       0
#XS Ineff= 2 , 0
         4958.05 2196.28 5047.35         2200.46
Permanent Ineff=
       F       F
Bank Sta=5008.4,5012.4
XS Rating Curve= 0 ,0
Exp/Cntr=0.3,0.1

Type RM Length L Ch R = 1 ,16593   ,441,441,441
BEGIN DESCRIPTION:
Indian Creek 01 36.0
END DESCRIPTION:
XS GIS Cut Line= 3
      1789525.01     13949724.96        1789575.       13949425.
      1789375.03     13949125.04
#Sta/Elev= 30
  4695.8 2201.13  4705.9 2200.34  4736.3  2199.7  4766.7 2196.65  4845.3 2192.02
  4850.4 2192.26  4878.2 2190.11  4928.9 2187.82  4966.9 2187.64  5002.9 2186.76
  5005.4 2186.18  5005.7 2185.68  5009.2 2185.68  5009.4 2186.18  5043.5 2187.84
    5072 2187.56  5100.5 2188.58  5115.6  2189.8  5121.6 2189.56  5187.7 2194.67
  5208.7 2195.25  5223.7    2197  5244.8 2197.71  5259.8 2199.18  5288.3 2200.58
  5316.9 2202.77  5331.9 2204.94  5352.9 2205.88  5357.4 2206.93  5360.4 2206.93
#Mann= 3 ,-1 , 0
  4695.8      .1       0  5005.4     .05       0  5009.4      .1       0
Bank Sta=5005.4,5009.4
XS Rating Curve= 0 ,0
Exp/Cntr=0.3,0.1

Type RM Length L Ch R = 1 ,16152   ,406,406,406
BEGIN DESCRIPTION:
Indian Creek 01 35.0
END DESCRIPTION:
XS GIS Cut Line= 3
      1789837.33     13949716.81        1789975.       13949375.
      1789814.96     13949030.66
#Sta/Elev= 30
  4637.8 2195.65  4715.2 2191.79  4736.8 2189.23  4758.3 2188.03  4806.2 2187.01
  4889.5 2183.65  4908.2 2182.27  4982.7 2180.48    4983 2179.98  4986.5 2179.98
  4986.7 2180.48  4991.5 2180.94  4996.9 2180.49    5015 2181.83  5037.9 2180.79
  5043.4 2181.29  5050.4 2182.99  5127.6 2184.52  5157.8 2186.07  5163.4 2185.94
  5193.8 2187.96  5209.1 2188.42  5277.8 2193.92  5283.3 2193.63  5311.7 2195.21
  5329.1  2196.5  5337.1 2196.35  5374.9 2199.44  5380.9 2200.41    5386 2200.41
#Mann= 4 ,-1 , 0
  4637.8      .1       0  4982.7     .05       0  4986.7      .1       0
  5311.7      .1       0
Bank Sta=4982.7,4986.7
XS Rating Curve= 0 ,0
Exp/Cntr=0.3,0.1

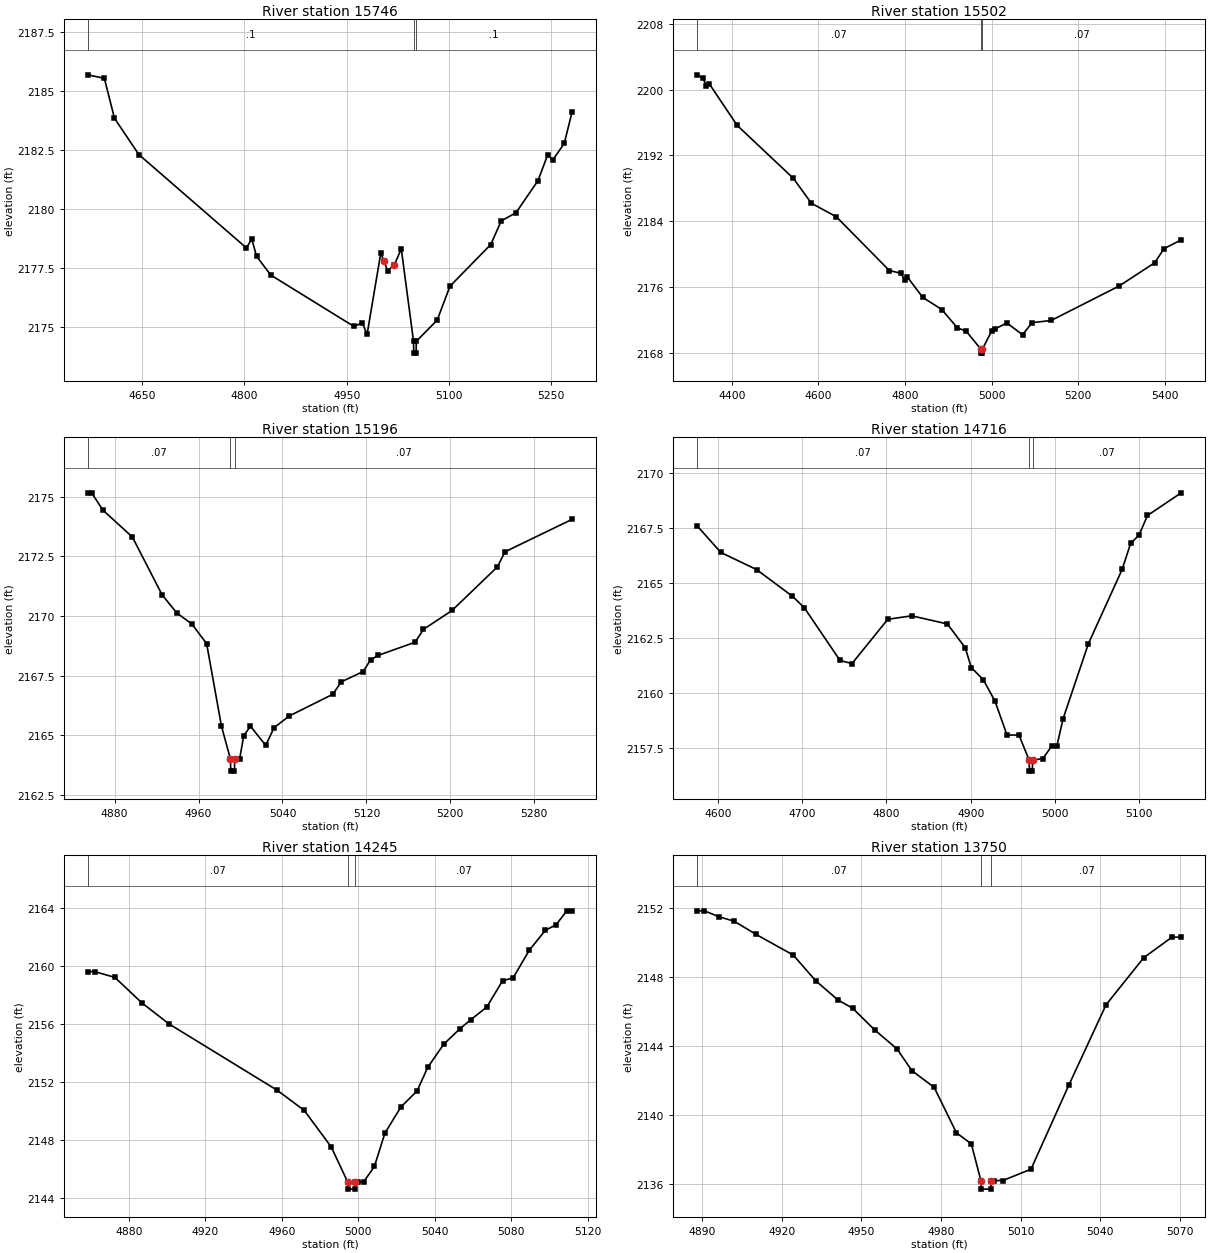
Type RM Length L Ch R = 1 ,15746   ,244,244,244
BEGIN DESCRIPTION:
Indian Creek 01 34.1
END DESCRIPTION:
XS GIS Cut Line= 4
      1790117.96     13949732.35      1790348.37     13949401.97
       1790339.2     13949292.46      1790266.04     13949108.35
#Sta/Elev= 30
  4570.2  2185.7  4594.4 2185.55  4609.2 2183.86    4645 2182.32  4802.9 2178.36
  4810.8 2178.74  4817.7 2178.01  4838.6 2177.21  4960.8 2175.03    4973 2175.19
    4980 2174.69  5000.1 2178.14 5004.64 2177.82  5010.1 2177.39  5020.1 2177.65
  5030.2 2178.32  5048.2  2174.4  5048.5  2173.9    5052  2173.9  5052.2  2174.4
  5082.9  2175.3  5101.7 2176.74  5161.4  2178.5    5177 2179.51  5198.5 2179.85
  5230.8 2181.21  5245.1 2182.31  5252.3 2182.08  5269.4 2182.79    5281 2184.14
#Mann= 3 ,-1 , 0
  4570.2      .1       0  5048.2     .05       0  5052.2      .1       0
#Block Obstruct= 2 , 0
         5000.23 2178.14 5030.45         2178.32
Bank Sta=5004.64,5020.1
XS Rating Curve= 0 ,0
Exp/Cntr=0.3,0.1

Type RM Length L Ch R = 1 ,15502   ,306,306,306
BEGIN DESCRIPTION:
Indian Creek 01 34.0
END DESCRIPTION:
XS GIS Cut Line= 3
      1790975.01     13949975.01       1790568.2     13949418.27
       1790363.3     13949041.18
#Sta/Elev= 30
  4319.4 2201.79  4332.9 2201.41  4341.4 2200.44  4347.6 2200.72  4412.5 2195.64
  4542.2 2189.21  4583.9 2186.18  4641.4 2184.54  4763.8 2178.01  4790.9 2177.67
  4799.4 2176.81  4805.6 2177.21  4841.1 2174.74  4885.1 2173.27  4920.6 2171.06
  4941.5 2170.63    4975 2168.47  4975.3 2167.97  4978.8 2167.97    4979 2168.47
  5000.1 2170.64  5008.9 2170.93  5035.4 2171.64  5071.6  2170.2  5093.5 2171.67
  5137.8 2171.94  5294.9 2176.13  5376.7 2178.95  5398.5 2180.67  5438.1 2181.73
#Mann= 3 ,-1 , 0
  4319.4     .07       0    4975     .05       0    4979     .07       0
Bank Sta=4975,4979
XS Rating Curve= 0 ,0
Exp/Cntr=0.3,0.1

Type RM Length L Ch R = 1 ,15196   ,480,480,480
BEGIN DESCRIPTION:
Indian Creek 01 33.0
END DESCRIPTION:
XS GIS Cut Line= 3
      1790925.01     13949375.01        1790825.       13949275.
        1790575.       13949075.
#Sta/Elev= 30
  4854.5 2175.16  4858.1 2175.16  4868.7 2174.44  4896.9 2173.31  4925.2 2170.89
  4939.4 2170.12  4953.5 2169.67  4967.7 2168.84  4981.8 2165.39  4990.4    2164
  4990.7  2163.5  4994.2  2163.5  4994.4    2164  4999.1    2164  5003.1 2164.99
  5009.5 2165.38    5024 2164.58    5032 2165.32  5046.4 2165.81    5088 2166.72
    5096 2167.24  5116.8 2167.67    5124 2168.16  5131.2 2168.35  5166.4  2168.9
  5174.4 2169.44  5201.6 2170.23  5244.9 2172.06  5252.1 2172.69  5316.1 2174.05
#Mann= 3 ,-1 , 0
  4854.5     .07       0  4990.4     .05       0  4994.4     .07       0
Bank Sta=4990.4,4994.4
XS Rating Curve= 0 ,0
Exp/Cntr=0.3,0.1

Type RM Length L Ch R = 1 ,14716   ,471,471,471
BEGIN DESCRIPTION:
Indian Creek 01 32.0
END DESCRIPTION:
XS GIS Cut Line= 3
      1791225.03     13949125.03        1790925.       13948825.
      1790775.01       13948825.
#Sta/Elev= 30
  4575.3 2167.63  4603.6 2166.41  4646.1 2165.63  4688.5 2164.42  4702.6  2163.9
    4745  2161.5  4759.2 2161.36  4801.6 2163.37  4829.9 2163.53  4872.3 2163.16
  4893.5 2162.08  4900.6 2161.18  4914.8 2160.63  4928.9 2159.64    4943 2158.11
  4957.2 2158.11  4969.3 2156.97  4969.6 2156.47  4973.1 2156.47  4973.3 2156.97
  4985.5 2157.04  4996.1 2157.61  5002.1 2157.61  5009.6 2158.86  5039.6 2162.27
  5079.6 2165.64  5089.6 2166.82  5099.6  2167.2  5109.6 2168.09  5149.6 2169.12
#Mann= 3 ,-1 , 0
  4575.3     .07       0  4969.3     .05       0  4973.3     .07       0
Bank Sta=4969.3,4973.3
XS Rating Curve= 0 ,0
Exp/Cntr=0.3,0.1

Type RM Length L Ch R = 1 ,14245   ,495,495,495
BEGIN DESCRIPTION:
Indian Creek 01 31.0
END DESCRIPTION:
XS GIS Cut Line= 3
      1791224.97     13948524.97        1791125.       13948425.
      1791024.98     13948374.99
#Sta/Elev= 30
  4858.6 2159.61  4862.1 2159.61  4872.7 2159.21  4886.8 2157.46    4901 2156.01
  4957.5 2151.45  4971.7 2150.06  4985.8 2147.55  4994.4 2145.14  4994.7 2144.64
  4998.2 2144.64  4998.4 2145.14    5000 2145.14  5002.8 2145.14  5008.4  2146.2
  5013.9 2148.49  5022.3  2150.3  5030.7 2151.39  5036.3 2153.02  5044.7 2154.62
  5053.1 2155.67  5058.7 2156.29  5067.1 2157.16  5075.4 2158.97    5081 2159.19
  5089.4 2161.08  5097.8 2162.45  5103.4 2162.83    5109 2163.79  5111.8 2163.79
#Mann= 3 ,-1 , 0
  4858.6     .07       0  4994.4     .05       0  4998.4     .07       0
Bank Sta=4994.4,4998.4
XS Rating Curve= 0 ,0
Exp/Cntr=0.3,0.1

Type RM Length L Ch R = 1 ,13750   ,440,440,440
BEGIN DESCRIPTION:
Indian Creek 01 30.0
END DESCRIPTION:
XS GIS Cut Line= 3
      1791524.99     13948174.98        1791475.       13948075.
      1791424.99     13948024.99
#Sta/Elev= 27
    4888 2151.84  4890.8 2151.84  4896.4 2151.49    4902 2151.24  4910.3 2150.47
  4924.3 2149.27  4932.7 2147.79  4941.1 2146.67  4946.7 2146.18  4955.1 2144.91
  4963.4 2143.82    4969 2142.56  4977.4 2141.59  4985.8 2138.95  4991.4 2138.31
    4995 2136.18  4995.2 2135.68  4998.7 2135.68    4999 2136.18  4999.8 2136.18
  5003.3 2136.18  5013.9 2136.84  5028.1  2141.7  5042.2 2146.39  5056.4 2149.12
    5067 2150.31  5070.5 2150.31
#Mann= 3 ,-1 , 0
    4888     .07       0    4995     .05       0    4999     .07       0
Bank Sta=4995,4999
XS Rating Curve= 0 ,0
Exp/Cntr=0.3,0.1

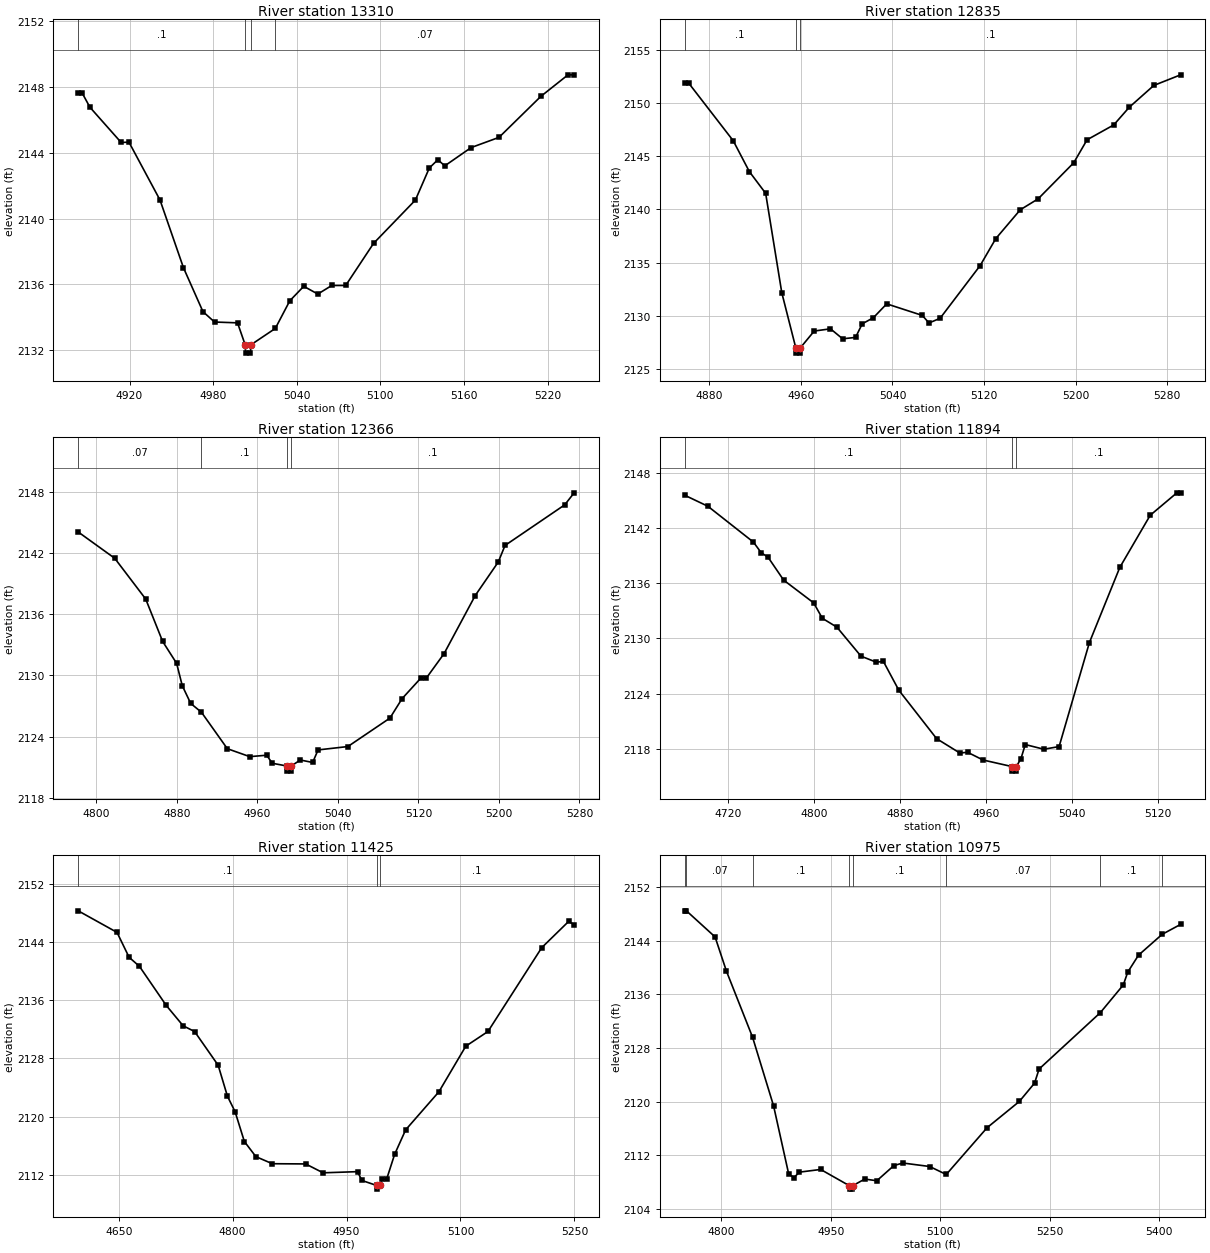
Type RM Length L Ch R = 1 ,13310   ,475,475,475
BEGIN DESCRIPTION:
Indian Creek 01 29.0
END DESCRIPTION:
XS GIS Cut Line= 3
      1791825.01     13947875.01        1791775.       13947775.
      1791531.16     13947766.71
#Sta/Elev= 30
  4883.2 2147.64    4886 2147.64  4891.6 2146.77    4914 2144.63  4919.6 2144.65
  4941.9 2141.13  4958.7 2137.02  4972.7 2134.35    4981 2133.72  4997.5 2133.67
    5003 2132.33  5003.3 2131.83  5006.8 2131.83    5007 2132.33  5024.6 2133.33
    5035 2135.01    5045 2135.89  5055.1 2135.42  5065.1 2135.94  5075.1 2135.94
  5095.1  2138.5  5125.1 2141.13  5135.1 2143.08  5141.2 2143.58  5146.2 2143.21
  5165.1 2144.32  5185.1 2144.94  5215.1 2147.43  5234.6 2148.74    5239 2148.74
#Mann= 4 ,-1 , 0
  4883.2      .1       0    5003     .05       0    5007      .1       0
  5024.6     .07       0
Bank Sta=5003,5007
XS Rating Curve= 0 ,0
Exp/Cntr=0.3,0.1

Type RM Length L Ch R = 1 ,12835   ,469,469,469
BEGIN DESCRIPTION:
Indian Creek 01 28.0
END DESCRIPTION:
XS GIS Cut Line= 3
      1792224.99     13947624.99        1792125.       13947525.
      1791874.96     13947374.97
#Sta/Elev= 30
  4858.6  2151.9  4862.1  2151.9    4901 2146.47  4915.1 2143.56  4929.3 2141.52
  4943.4 2132.15  4955.6 2126.97  4955.8 2126.47  4959.3 2126.47  4959.6 2126.97
  4971.7 2128.55  4985.9 2128.76  4996.5 2127.82  5007.8 2127.95  5013.6 2129.23
  5023.3  2129.8    5035 2131.11  5066.1 2130.02  5071.9 2129.31  5081.6 2129.75
  5116.6 2134.72  5130.2 2137.25  5151.6 2139.97  5167.2    2141  5198.3  2144.4
  5209.9 2146.56  5233.2 2147.96  5246.8 2149.63  5268.2 2151.68  5291.6 2152.68
#Mann= 3 ,-1 , 0
  4858.6      .1       0  4955.6     .05       0  4959.6      .1       0
Bank Sta=4955.6,4959.6
XS Rating Curve= 0 ,0
Exp/Cntr=0.3,0.1

Type RM Length L Ch R = 1 ,12366   ,472,472,472
BEGIN DESCRIPTION:
Indian Creek 01 27.0
END DESCRIPTION:
XS GIS Cut Line= 3
        1792475.     13947375.01        1792375.       13947175.
      1792274.99     13946924.98
#Sta/Elev= 30
  4781.9 2144.07  4818.2 2141.49    4849 2137.49  4865.8 2133.34  4879.7 2131.19
  4885.3    2129  4893.7 2127.26  4904.4 2126.39  4930.1 2122.82  4952.4 2122.04
  4969.2 2122.18  4974.8 2121.39  4989.5 2121.12  4989.8 2120.62  4993.3 2120.62
  4993.5 2121.12  5002.7 2121.71  5014.9 2121.47  5020.3  2122.7  5049.9 2123.03
  5091.7 2125.82  5103.8 2127.73  5122.6 2129.76    5128 2129.76  5145.5 2132.14
  5176.5 2137.84  5199.4 2141.13  5206.1 2142.75  5265.4 2146.73  5274.8 2147.91
#Mann= 4 ,-1 , 0
  4781.9     .07       0  4904.4      .1       0  4989.5     .05       0
  4993.5      .1       0
Bank Sta=4989.5,4993.5
XS Rating Curve= 0 ,0
Exp/Cntr=0.3,0.1

Type RM Length L Ch R = 1 ,11894   ,469,469,469
BEGIN DESCRIPTION:
Indian Creek 01 26.0
END DESCRIPTION:
XS GIS Cut Line= 3
      1792875.01     13947075.01        1792675.       13946825.
      1792574.99     13946724.99
#Sta/Elev= 30
  4679.6 2145.57  4701.2 2144.37  4743.6 2140.47  4750.8 2139.32  4757.2 2138.83
  4771.7 2136.34  4799.7 2133.86  4807.7 2132.19  4821.3 2131.22  4843.7 2128.07
  4858.1 2127.41  4864.5 2127.51  4878.9 2124.37  4914.1  2119.1  4935.7 2117.54
  4942.9 2117.62  4957.3 2116.78  4984.1 2116.07  4984.4 2115.57    4988 2115.57
  4988.3 2116.07  4992.6 2116.93  4996.6 2118.46  5013.9 2117.95  5028.1 2118.24
  5056.3 2129.55  5084.6 2137.72  5112.9 2143.39  5137.7 2145.83  5141.2 2145.83
#Mann= 3 ,-1 , 0
  4679.6      .1       0  4984.1     .05       0  4988.3      .1       0
Bank Sta=4984.1,4988.3
XS Rating Curve= 0 ,0
Exp/Cntr=0.3,0.1

Type RM Length L Ch R = 1 ,11425   ,450,450,450
BEGIN DESCRIPTION:
Indian Creek 01 25.0
END DESCRIPTION:
XS GIS Cut Line= 3
      1793375.01       13946725.        1793025.       13946525.
      1792875.01     13946325.02
#Sta/Elev= 30
  4596.6 2148.26  4647.7  2145.3  4663.6 2141.88  4677.2 2140.64  4712.5 2135.27
  4734.8 2132.47  4749.9 2131.68  4780.9 2127.05  4793.1  2122.8  4803.2 2120.67
  4815.4 2116.58  4830.6  2114.5  4852.2 2113.53  4896.1  2113.5  4919.1 2112.28
  4964.4 2112.44  4970.2 2111.23  4989.7 2110.54    4990 2110.04  4993.9 2110.54
  4996.8 2111.42  5002.8 2111.42  5013.3 2114.82  5027.8 2118.18  5071.6 2123.41
    5107 2129.67  5136.2 2131.69    5207  2143.2  5242.4  2146.8  5249.7 2146.37
#Mann= 3 ,-1 , 0
  4596.6      .1       0  4989.7     .05       0  4993.9      .1       0
Bank Sta=4989.7,4993.9
XS Rating Curve= 0 ,0
Exp/Cntr=0.3,0.1

Type RM Length L Ch R = 1 ,10975   ,471,471,471
BEGIN DESCRIPTION:
Indian Creek 01 24.0
END DESCRIPTION:
XS GIS Cut Line= 3
      1793575.02     13946425.01        1793375.       13946275.
      1793025.03     13946025.02
#Sta/Elev= 30
  4749.7 2148.45  4752.1 2148.45  4791.4 2144.56    4807 2139.45  4842.8 2129.62
  4871.6  2119.4  4892.4 2109.21  4899.7 2108.72    4907 2109.52  4936.2 2109.92
  4975.7 2107.49    4976 2106.99  4979.7 2106.99    4980 2107.49  4996.6 2108.49
  5013.2 2108.24  5036.6  2110.5  5048.9 2110.88  5085.7 2110.36  5108.4 2109.17
  5164.4 2116.14  5208.6 2120.05  5229.5 2122.78  5235.7 2124.88  5319.7 2133.28
  5351.2 2137.41  5357.3 2139.32  5372.1 2141.85  5404.5 2144.95  5429.8 2146.43
#Mann= 8 ,-1 , 0
  4749.7      .1       0  4752.1     .07       0  4842.8      .1       0
  4975.7     .05       0    4980      .1       0  5108.4     .07       0
  5319.7      .1       0  5404.5     .07       0
Bank Sta=4975.7,4980
XS Rating Curve= 0 ,0
Exp/Cntr=0.3,0.1

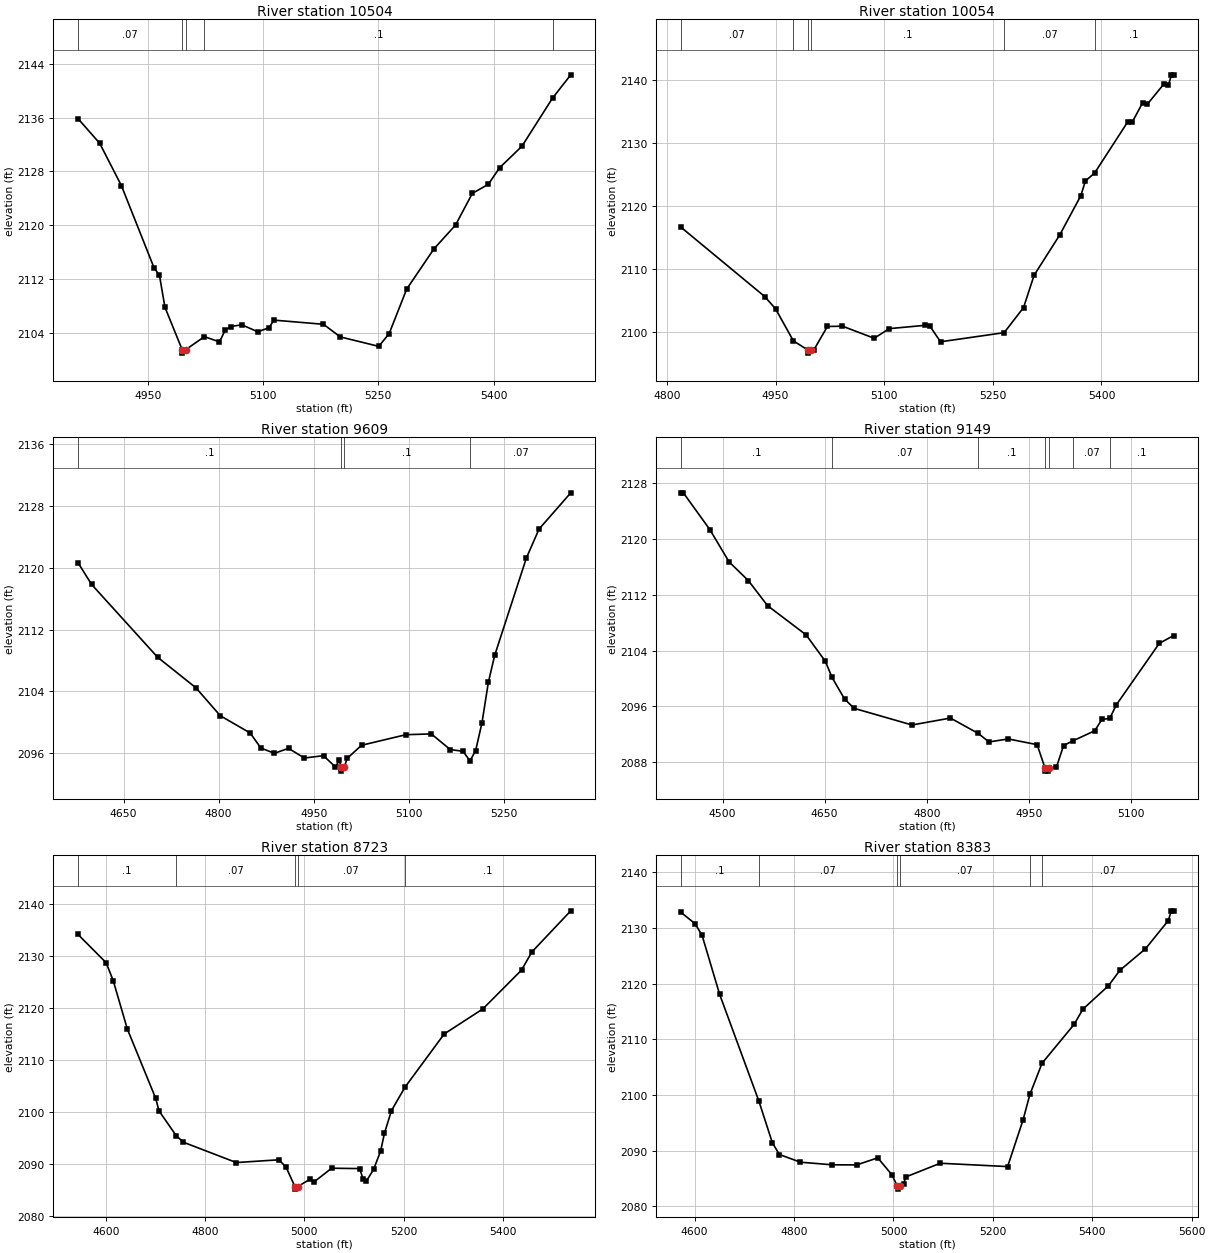
Type RM Length L Ch R = 1 ,10504   ,450,450,450
BEGIN DESCRIPTION:
Indian Creek 01 23.0
END DESCRIPTION:
XS GIS Cut Line= 3
      1793774.97     13946074.97        1793675.       13945975.
      1793274.98     13945674.99
#Sta/Elev= 30
  4859.1 2135.86  4887.3 2132.19  4915.6 2125.88    4958 2113.68  4965.1 2112.54
  4972.2 2107.81  4994.7 2101.48    4995 2100.98  4999.1 2101.48  5023.6 2103.43
  5043.2 2102.65  5050.5 2104.36  5057.8 2104.94  5072.4 2105.19  5093.2 2104.15
  5107.8 2104.77    5114 2105.89  5178.6 2105.27  5200.5 2103.39  5250.5 2101.99
    5264 2103.86  5286.9  2110.5  5322.4 2116.49  5350.5 2120.03  5372.4 2124.75
  5393.2 2126.09  5407.8 2128.55  5436.9 2131.75  5476.8 2138.92  5500.5 2142.38
#Mann= 5 ,-1 , 0
  4859.1     .07       0  4994.7     .05       0  4999.1     .07       0
  5023.6      .1       0  5476.8     .07       0
Bank Sta=4994.7,4999.1
XS Rating Curve= 0 ,0
Exp/Cntr=0.3,0.1

Type RM Length L Ch R = 1 ,10054   ,445,445,445
BEGIN DESCRIPTION:
Indian Creek 01 22.0
END DESCRIPTION:
XS GIS Cut Line= 3
      1793925.02     13945725.03        1793825.       13945575.
      1793425.01     13945275.01
#Sta/Elev= 30
  4819.4 2116.67  4935.1 2105.65  4950.1 2103.69  4974.6 2098.62  4994.5 2097.17
  4994.8 2096.67  4998.9 2097.17  5002.8 2097.17  5021.6  2100.9  5042.4 2100.95
  5086.2 2099.03    5107 2100.56    5156 2101.08  5163.3 2100.93  5177.8 2098.47
  5265.6 2099.92  5292.4  2103.9    5307 2109.04  5342.4 2115.44  5371.6  2121.7
  5377.8 2124.01  5390.6 2125.28  5436.2 2133.39  5442.4 2133.34    5457 2136.47
  5463.3  2136.2  5486.2 2139.41  5492.4 2139.19  5496.6 2140.87  5499.7 2140.87
#Mann= 6 ,-1 , 0
  4819.4     .07       0  4974.6      .1       0  4994.5     .05       0
  4998.9      .1       0  5265.6     .07       0  5390.6      .1       0
Bank Sta=4994.5,4998.9
XS Rating Curve= 0 ,0
Exp/Cntr=0.3,0.1

Type RM Length L Ch R = 1 ,9609    ,460,460,460
BEGIN DESCRIPTION:
Indian Creek 01 21.0
END DESCRIPTION:
XS GIS Cut Line= 3
      1794275.02     13945375.01        1793875.       13945225.
      1793525.03       13945225.
#Sta/Elev= 30
  4578.3 2120.67  4599.7 2117.86  4703.8 2108.43  4764.3 2104.47  4802.6 2100.86
  4849.8 2098.62  4866.7 2096.67    4888 2095.99  4910.3 2096.63  4935.2 2095.38
  4965.5 2095.68  4984.2 2094.22  4990.4 2095.06  4993.4 2094.18  4993.7 2093.68
  4998.1 2094.18  5002.9 2095.34  5025.5 2097.03  5095.5  2098.4  5135.5  2098.5
  5165.5 2096.47  5185.5 2096.25  5196.6 2095.01  5205.5 2096.35  5215.5 2099.96
  5225.5 2105.17  5235.5 2108.68  5285.5 2121.29  5305.5 2125.04  5355.5 2129.73
#Mann= 4 ,-1 , 0
  4578.3      .1       0  4993.4     .05       0  4998.1      .1       0
  5196.6     .07       0
Bank Sta=4993.4,4998.1
XS Rating Curve= 0 ,0
Exp/Cntr=0.3,0.1

Type RM Length L Ch R = 1 ,9149    ,426,426,426
BEGIN DESCRIPTION:
Indian Creek 01 20.0
END DESCRIPTION:
XS GIS Cut Line= 3
      1794424.97     13945224.97        1794025.       13944825.
      1793974.99     13944674.96
#Sta/Elev= 30
  4438.9  2126.6  4442.4  2126.6  4481.3 2121.34  4509.6 2116.71  4537.9 2114.03
  4566.1 2110.44  4622.7 2106.26    4651 2102.47  4660.9 2100.15  4679.3 2097.06
  4693.4 2095.73  4778.3 2093.35  4834.8 2094.34  4875.4 2092.15  4891.4 2090.92
  4919.7 2091.35  4962.1 2090.53  4973.5 2087.24  4973.9 2086.74  4978.6 2086.74
  4979.1 2087.24  4990.4 2087.28    5001 2090.41    5015 2091.09  5046.7 2092.52
  5057.3 2094.14  5068.9  2094.3  5078.3 2096.21  5141.6 2105.04  5162.7 2106.16
#Mann= 7 ,-1 , 0
  4438.9      .1       0  4660.9     .07       0  4875.4      .1       0
  4973.5     .05       0  4979.1      .1       0    5015     .07       0
  5068.9      .1       0
Bank Sta=4973.5,4979.1
XS Rating Curve= 0 ,0
Exp/Cntr=0.3,0.1

Type RM Length L Ch R = 1 ,8723    ,340,340,340
BEGIN DESCRIPTION:
Indian Creek 01 19.0
END DESCRIPTION:
XS GIS Cut Line= 3
      1794724.98     13944974.98        1794375.       13944675.
      1793974.97     13944324.97
#Sta/Elev= 30
  4544.3 2134.12  4600.8  2128.7  4615.1 2125.26  4643.6 2115.93  4700.7 2102.61
  4707.3  2100.2  4742.3  2095.4  4756.7 2094.16  4863.1 2090.26  4948.7 2090.79
    4963 2089.44  4981.1 2085.65  4981.5 2085.15  4986.7 2085.65  5012.4 2087.08
    5019 2086.48  5055.1 2089.17  5111.6  2089.1  5118.7 2087.02  5125.3 2086.71
  5139.6 2088.94  5153.8 2092.46  5161.4 2095.86  5175.6 2100.24  5202.7 2104.73
  5281.9 2114.99  5359.8 2119.81  5437.6 2127.27  5458.5 2130.76  5536.8 2138.67
#Mann= 5 ,-1 , 0
  4544.3      .1       0  4742.3     .07       0  4981.1     .05       0
  4986.7     .07       0  5202.7      .1       0
Bank Sta=4981.1,4986.7
XS Rating Curve= 0 ,0
Exp/Cntr=0.3,0.1

Type RM Length L Ch R = 1 ,8383    ,590,590,590
BEGIN DESCRIPTION:
Indian Creek 01 18.0
END DESCRIPTION:
XS GIS Cut Line= 3
      1794925.02     13944775.02      1794608.67     13944463.09
      1794111.33     13944235.03
#Sta/Elev= 30
  4572.4 2132.83  4600.7 2130.81  4614.8 2128.73  4650.2 2118.11  4729.2 2098.93
  4756.2 2091.47  4770.4 2089.34  4812.8 2087.96  4876.5 2087.49    4926 2087.47
  4968.4 2088.74  4996.7 2085.72    5008 2083.62  5008.5 2083.12  5013.6 2083.62
  5020.4  2084.1  5025.1 2085.32  5094.1 2087.77  5229.7 2087.17  5260.6 2095.51
  5274.5 2100.13    5299 2105.74  5363.6 2112.72  5381.1 2115.44  5432.6 2119.65
  5455.6 2122.43  5507.1 2126.29  5553.1 2131.37    5559 2133.11  5563.8 2133.11
#Mann= 6 ,-1 , 0
  4572.4      .1       0  4729.2     .07       0    5008     .05       0
  5013.6     .07       0  5274.5      .1       0    5299     .07       0
Bank Sta=5008,5013.6
XS Rating Curve= 0 ,0
Exp/Cntr=0.3,0.1

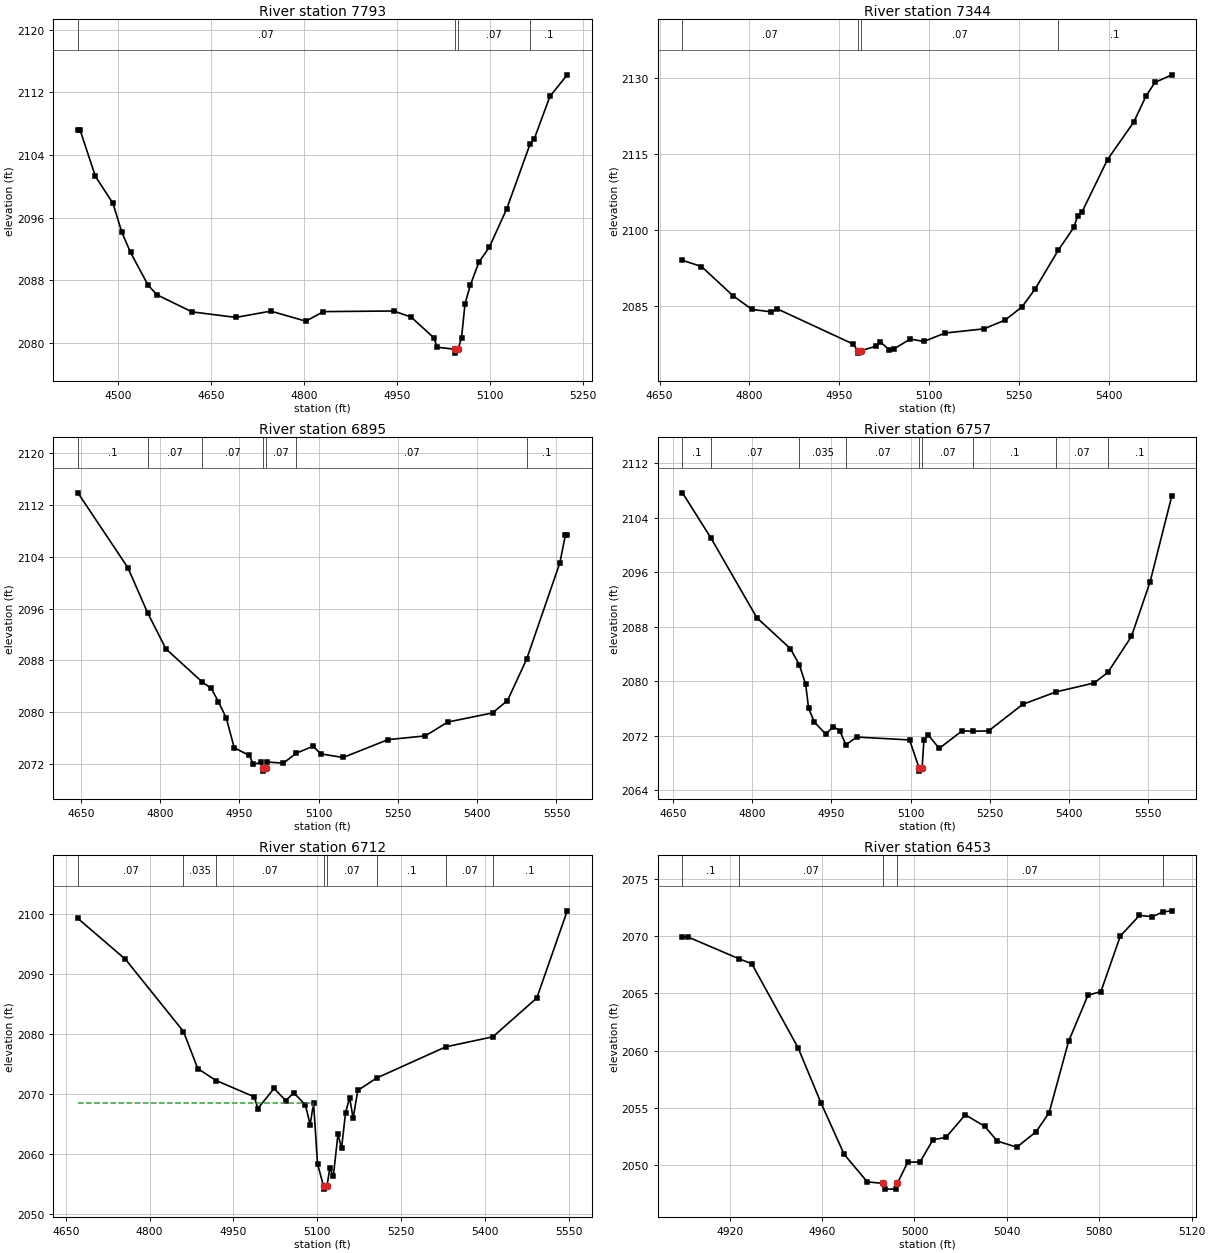
Type RM Length L Ch R = 1 ,7793    ,449,449,449
BEGIN DESCRIPTION:
Indian Creek 01 17.0
END DESCRIPTION:
XS GIS Cut Line= 3
      1795175.03     13944425.03        1794775.       13944025.
      1794575.03     13943925.01
#Sta/Elev= 30
  4434.7 2107.16  4438.3 2107.16    4463 2101.24  4491.3 2097.82  4505.4 2094.16
  4519.6 2091.54  4547.9 2087.37    4562 2086.15  4618.6 2083.96  4689.3 2083.25
  4745.9 2084.05  4802.4 2082.77  4830.7 2083.99  4943.9 2084.07  4972.1  2083.3
  5008.8 2080.65  5014.4 2079.44  5042.3 2079.19  5042.7 2078.69    5048 2079.19
  5053.5 2080.67  5059.1 2084.98  5067.5 2087.33  5081.5 2090.31  5098.3 2092.21
  5126.2 2097.08  5163.8 2105.33  5170.9 2106.07  5196.1 2111.48    5224 2114.22
#Mann= 4 ,-1 , 0
  4434.7     .07       0  5042.3     .05       0    5048     .07       0
  5163.8      .1       0
Bank Sta=5042.3,5048
XS Rating Curve= 0 ,0
Exp/Cntr=0.3,0.1

Type RM Length L Ch R = 1 ,7344    ,449,449,449
BEGIN DESCRIPTION:
Indian Creek 01 16.0
END DESCRIPTION:
XS GIS Cut Line= 3
      1795275.01     13944275.04        1795175.       13943975.
      1794874.98     13943574.98
#Sta/Elev= 30
  4688.3 2094.02    4720  2092.8  4772.7 2087.03  4804.3 2084.34  4835.9 2083.87
  4846.5 2084.45  4972.9 2077.52  4980.6 2076.23    4981 2075.73  4986.4 2076.23
  5011.9 2077.12  5018.1 2077.97  5032.7 2076.44    5041 2076.55  5068.1  2078.5
    5091 2078.03  5126.4 2079.69    5191 2080.51  5226.4 2082.24  5254.6 2084.84
  5276.4 2088.35  5315.1    2096    5341 2100.49  5347.3 2102.69  5354.6 2103.51
  5397.3 2113.88    5441 2121.26  5461.9 2126.48  5476.4 2129.08  5504.6 2130.58
#Mann= 4 ,-1 , 0
  4688.3     .07       0  4980.6     .05       0  4986.4     .07       0
  5315.1      .1       0
Bank Sta=4980.6,4986.4
XS Rating Curve= 0 ,0
Exp/Cntr=0.3,0.1

Type RM Length L Ch R = 1 ,6895    ,138,138,138
BEGIN DESCRIPTION:
Indian Creek 01 15.0
END DESCRIPTION:
XS GIS Cut Line= 3
      1795774.99     13944124.99        1795575.       13943825.
      1795175.02     13943425.02
#Sta/Elev= 30
  4644.2 2113.83  4738.8  2102.3  4776.3 2095.32  4810.9 2089.78  4879.5 2084.69
  4896.6 2083.69  4910.1 2081.67  4925.1 2079.12  4940.1 2074.55  4968.7 2073.36
  4976.2 2072.01  4991.2  2072.3  4994.2 2071.45  4994.7 2070.95  5000.2 2071.45
  5001.7 2072.36    5033 2072.18  5057.7 2073.72  5089.6 2074.79  5103.7 2073.61
  5146.2 2073.05    5231  2075.8  5301.7 2076.38  5344.2 2078.51    5429 2079.92
  5457.3 2081.83  5493.4 2088.17  5556.3 2103.01  5566.9 2107.33  5570.4 2107.33
#Mann= 7 ,-1 , 0
  4644.2      .1       0  4776.3     .07       0  4879.5     .07       0
  4994.2     .05       0  5000.2     .07       0  5057.7     .07       0
  5493.4      .1       0
Bank Sta=4994.2,5000.2
XS Rating Curve= 0 ,0
Exp/Cntr=0.3,0.1

Type RM Length L Ch R = 1 ,6757    ,45,45,45
BEGIN DESCRIPTION:
Indian Creek 01 14.2
END DESCRIPTION:
XS GIS Cut Line= 3
      1795823.65     13944044.12      1795705.37     13943773.93
      1795198.77     13943393.98
#Sta/Elev= 30
  4667.4 2107.65    4721 2101.07  4808.4 2089.32  4872.2 2084.77  4888.8 2082.44
    4901 2079.57  4906.6 2076.03  4917.5    2074  4939.3 2072.23  4953.3 2073.33
  4965.6 2072.75  4977.2 2070.67  4998.1  2071.8  5098.1 2071.38    5116  2067.3
  5116.5  2066.8    5122  2067.3  5125.3 2071.37  5133.6  2072.1  5154.4 2070.14
  5198.1 2072.73    5218 2072.64  5248.1 2072.71  5312.7  2076.6    5376 2078.43
  5448.1 2079.74  5474.3 2081.29    5519 2086.58  5554.4  2094.6  5595.6 2107.22
#Mann= 9 ,-1 , 0
  4667.4      .1       0    4721     .07       0  4888.8    .035       0
  4977.2     .07       0    5116     .05       0    5122     .07       0
    5218      .1       0    5376     .07       0  5474.3      .1       0
Bank Sta=5116,5122
XS Rating Curve= 0 ,0
Exp/Cntr=0.3,0.1

Type RM Length L Ch R = 1 ,6712    ,259,259,259
BEGIN DESCRIPTION:
Indian Creek 01 14.1
END DESCRIPTION:
XS GIS Cut Line= 3
      1795878.01      13943960.9      1795727.44     13943745.55
      1795238.71     13943375.49
#Sta/Elev= 30
  4671.6 2099.21  4756.8  2092.4  4860.6 2080.37  4886.2  2074.2    4919 2072.22
  4987.3  2069.5  4993.6 2067.54  5022.7  2070.9  5043.5 2068.88  5058.1 2070.17
  5078.9 2068.12  5087.2 2064.86  5093.4 2068.45  5100.5 2058.31  5111.3 2054.63
  5111.8 2054.13  5117.3 2054.63  5122.5 2057.59  5128.8  2056.3  5137.1  2063.3
  5143.4  2060.9  5150.7 2066.88  5157.9 2069.37  5164.2 2065.94  5172.5 2070.57
  5206.4 2072.64  5330.1 2077.83  5414.3  2079.5  5492.9 2085.96  5547.4 2100.48
#Mann= 8 ,-1 , 0
  4671.6     .07       0  4860.6    .035       0    4919     .07       0
  5111.3     .05       0  5117.3     .07       0  5206.4      .1       0
  5330.1     .07       0  5414.3      .1       0
#XS Ineff= 2 , 0
         5091.89 2068.45 5157.84         2069.18
Permanent Ineff=
       F       F
Bank Sta=5111.3,5117.3
XS Rating Curve= 0 ,0
Exp/Cntr=0.3,0.1

Type RM Length L Ch R = 1 ,6453    ,478,478,478
BEGIN DESCRIPTION:
Indian Creek 01 14.0
END DESCRIPTION:
XS GIS Cut Line= 3
      1795775.01       13943475.        1795675.       13943475.
      1795575.01     13943425.01
#Sta/Elev= 30
  4899.6 2069.91  4902.1 2069.91  4924.1 2068.01  4929.6 2067.58  4949.6 2060.26
  4959.6 2055.41  4969.6 2050.94  4979.6 2048.54  4986.6 2048.41  4987.1 2047.91
  4992.1 2047.91  4992.6 2048.41  4997.1 2050.27  5002.4 2050.27    5008 2052.22
  5013.6 2052.42    5022  2054.4  5030.4 2053.39  5035.9  2052.1  5044.3 2051.57
  5052.7 2052.93  5058.3 2054.59  5066.7  2060.8  5075.1 2064.84  5080.7 2065.15
  5089.1    2070  5097.4  2071.8    5103 2071.69  5107.6 2072.11  5111.4  2072.2
#Mann= 5 ,-1 , 0
  4899.6      .1       0  4924.1     .07       0  4986.6     .05       0
  4992.6     .07       0  5107.6      .1       0
Bank Sta=4986.6,4992.6
XS Rating Curve= 0 ,0
Exp/Cntr=0.3,0.1