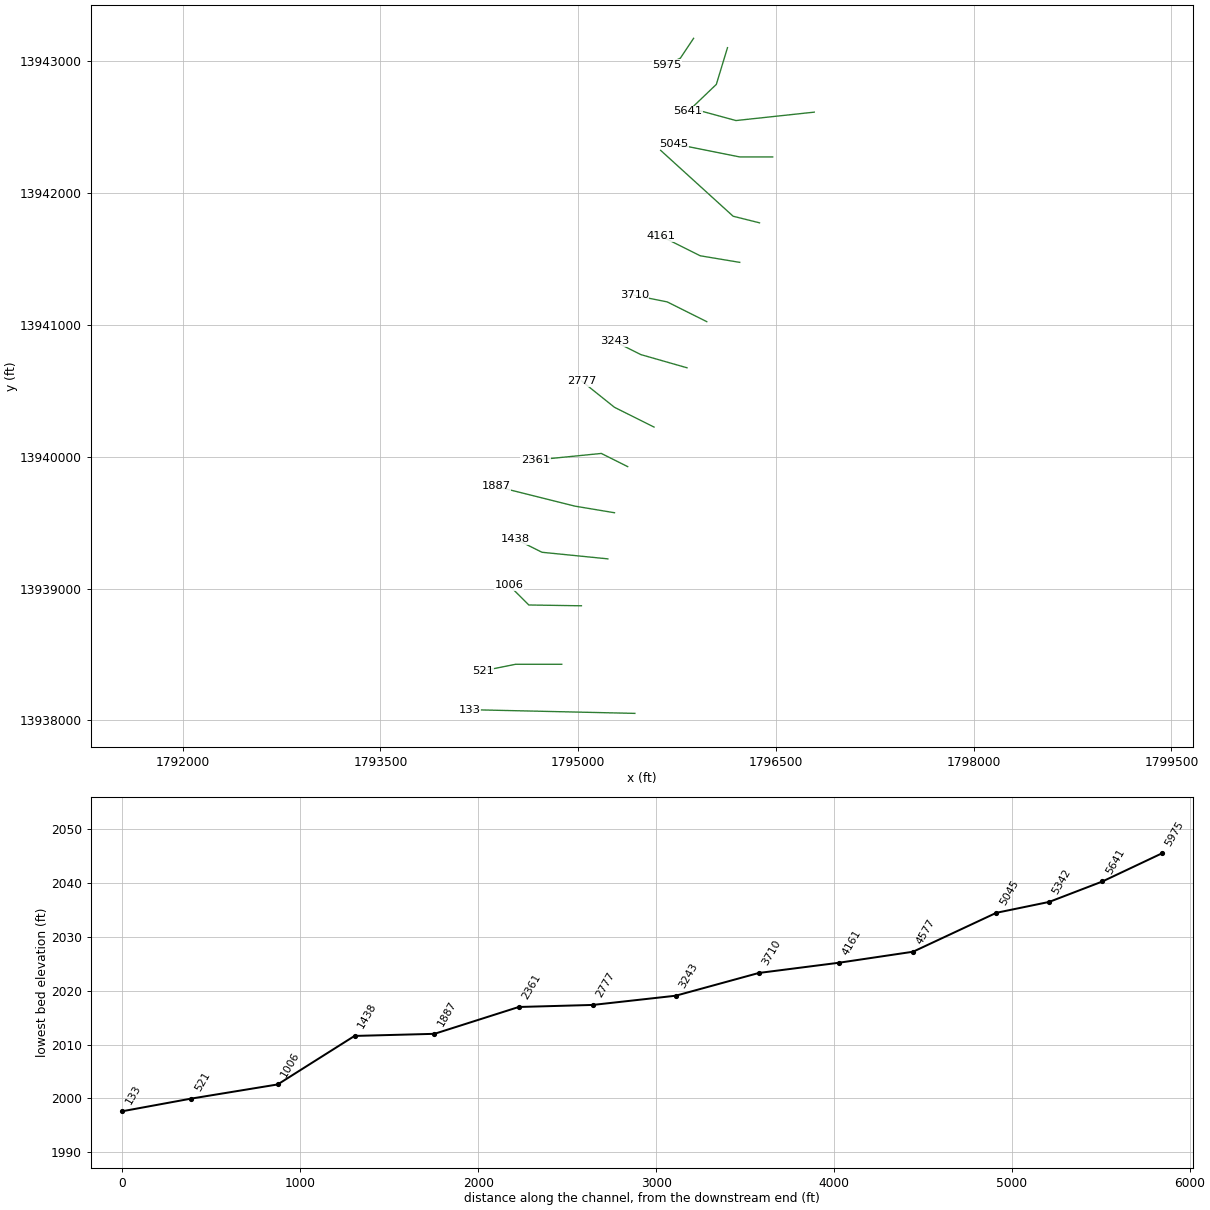
HEC-RAS study Indian Creek 01.prj: Indian Creek 01 Base Level Engineering

--- Indian Creek 01.g01 (geometry) --- (continued)

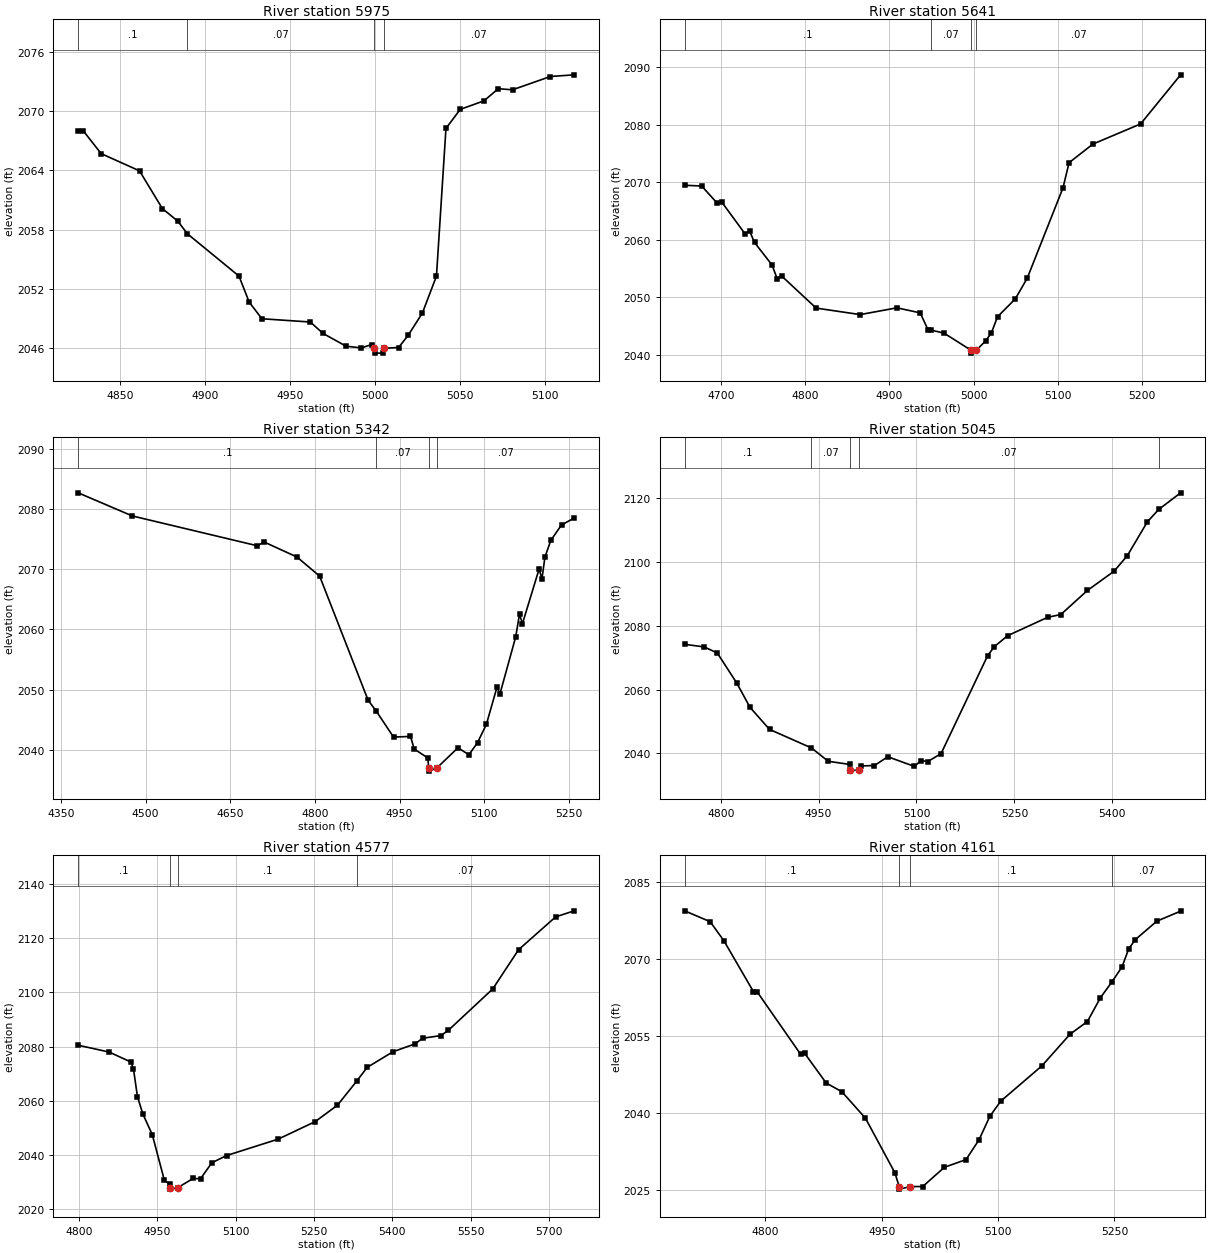
Type RM Length L Ch R = 1 ,5975    ,334,334,334
BEGIN DESCRIPTION:
Indian Creek 01 13.0
END DESCRIPTION:
XS GIS Cut Line= 3
      1795875.01     13943175.01        1795775.       13943025.
        1795675.       13942975.
#Sta/Elev= 30
  4825.1 2068.02  4828.1 2068.02  4838.6 2065.71  4861.2 2063.96  4874.7 2060.12
  4883.7 2058.86  4889.4 2057.57  4919.8 2053.27  4925.8 2050.63  4933.3 2048.94
  4961.8 2048.61  4969.3 2047.45  4982.9 2046.15  4991.9 2045.98  4997.9 2046.32
  4999.3 2045.95  4999.8 2045.45  5004.9 2045.45  5005.4 2045.95  5013.8 2046.02
  5019.4 2047.25  5027.8 2049.52  5036.1 2053.27  5041.7 2068.27  5050.1  2070.2
  5064.1 2071.07  5072.5  2072.3  5080.9 2072.19  5103.2 2073.54  5117.2 2073.71
#Mann= 4 ,-1 , 0
  4825.1      .1       0  4889.4     .07       0  4999.3     .05       0
  5005.4     .07       0
Bank Sta=4999.3,5005.4
XS Rating Curve= 0 ,0
Exp/Cntr=0.3,0.1

Type RM Length L Ch R = 1 ,5641    ,299,299,299
BEGIN DESCRIPTION:
Indian Creek 01 12.1
END DESCRIPTION:
XS GIS Cut Line= 3
      1796132.19     13943104.29      1796047.55      13942825.6
      1795832.79     13942619.95
#Sta/Elev= 30
    4657 2069.47  4677.2 2069.34  4695.9  2066.3  4701.1 2066.53  4728.8 2060.98
    4734 2061.52  4739.9 2059.51  4760.8 2055.56  4766.9 2053.12  4772.1 2053.67
    4813 2048.08  4865.3 2046.95  4908.9 2048.13  4936.5 2047.25    4946 2044.25
  4949.6 2044.25  4964.8 2043.72  4996.9 2040.74  4997.4 2040.24    5003 2040.74
  5014.1 2042.34  5021.1 2043.79  5028.3 2046.57  5049.4 2049.69  5063.5 2053.27
    5106 2069.02  5113.2  2073.4  5141.5 2076.64  5198.1 2080.15  5245.6  2088.7
#Mann= 4 ,-1 , 0
    4657      .1       0  4949.6     .07       0  4996.9     .05       0
    5003     .07       0
#Block Obstruct= 2 , 0
         4898.16 2047.91
Bank Sta=4996.9,5003
XS Rating Curve= 0 ,0
Exp/Cntr=0.3,0.1

Type RM Length L Ch R = 1 ,5342    ,297,297,297
BEGIN DESCRIPTION:
Indian Creek 01 12.0
END DESCRIPTION:
XS GIS Cut Line= 3
      1796790.26     13942614.93      1796196.71      13942551.1
      1795925.05     13942624.99
#Sta/Elev= 30
  4380.8 2082.67  4476.6 2078.83  4697.9 2073.88  4710.2  2074.5  4768.3 2072.01
  4808.5 2068.83  4894.3 2048.23    4909 2046.38  4939.3 2042.11  4969.4 2042.21
  4976.1 2040.11  5000.3 2038.63  5001.4 2036.95  5001.9 2036.45  5015.8 2036.95
  5053.5 2040.33  5072.8 2039.17  5088.1 2041.17  5103.9 2044.24  5122.7 2050.43
  5127.9 2049.29  5155.7 2058.72  5162.5 2062.52  5167.7 2060.94  5197.1 2069.98
  5202.3 2068.41  5207.5 2071.98  5217.9 2074.76  5236.9 2077.34  5259.3 2078.47
#Mann= 4 ,-1 , 0
  4380.8      .1       0    4909     .07       0  5001.4     .05       0
  5015.8     .07       0
Bank Sta=5001.4,5015.8
XS Rating Curve= 0 ,0
Exp/Cntr=0.3,0.1

Type RM Length L Ch R = 1 ,5045    ,468,468,468
BEGIN DESCRIPTION:
Indian Creek 01 11.0
END DESCRIPTION:
XS GIS Cut Line= 3
      1796475.02       13942275.        1796225.       13942275.
      1795725.02       13942375.
#Sta/Elev= 30
  4744.8 2074.23  4774.8 2073.41  4794.8  2071.5  4824.8 2062.01  4844.8 2054.47
  4874.8 2047.53  4939.1  2041.7  4964.8 2037.52  4997.4 2036.54  4997.8 2034.93
  4998.3 2034.43  5012.2 2034.93  5015.2 2036.06  5035.6 2036.19    5056 2038.95
  5096.8 2035.91    5107 2037.76  5117.2 2037.43  5137.6 2039.91    5209 2070.67
  5219.2 2073.48  5239.6 2076.94  5300.8 2082.69  5321.2 2083.59  5361.9 2091.14
  5402.7 2097.17  5423.1 2102.07  5453.7 2112.66  5471.1 2116.56  5504.7 2121.78
#Mann= 5 ,-1 , 0
  4744.8      .1       0  4939.1     .07       0  4997.8     .05       0
  5012.2     .07       0  5471.1      .1       0
Bank Sta=4997.8,5012.2
XS Rating Curve= 0 ,0
Exp/Cntr=0.3,0.1

Type RM Length L Ch R = 1 ,4577    ,416,416,416
BEGIN DESCRIPTION:
Indian Creek 01 10.0
END DESCRIPTION:
XS GIS Cut Line= 3
      1796375.03     13941774.99        1796175.       13941825.
      1795624.99     13942325.01
#Sta/Elev= 30
  4798.5 2080.47  4857.8 2077.95    4899 2074.29  4904.2 2071.85  4911.9 2061.46
  4922.2 2055.05  4940.3 2047.38  4963.5 2030.44  4973.8 2029.03  4974.2 2027.71
  4974.7 2027.21  4988.7 2027.71  5018.5 2031.16  5032.7 2031.05  5054.3 2036.96
  5082.7 2039.65  5181.4 2045.72  5252.3 2052.21  5294.9  2058.3  5332.3 2067.33
  5351.7 2072.28    5401 2078.05  5443.6    2081  5457.8 2083.06  5492.9 2084.05
  5507.1 2085.99  5592.2 2101.33  5641.6 2115.84  5712.5 2127.98    5748 2130.23
#Mann= 4 ,-1 , 0
  4798.5      .1       0  4974.2     .05       0  4988.7      .1       0
  5332.3     .07       0
Bank Sta=4974.2,4988.7
XS Rating Curve= 0 ,0
Exp/Cntr=0.3,0.1

Type RM Length L Ch R = 1 ,4161    ,451,451,451
BEGIN DESCRIPTION:
Indian Creek 01 9.0
END DESCRIPTION:
XS GIS Cut Line= 3
      1796224.97     13941475.01        1795925.       13941525.
      1795625.01     13941674.99
#Sta/Elev= 30
  4695.9 2079.45  4728.8 2077.33  4746.6 2073.58  4784.6 2063.68  4789.6  2063.6
  4845.4 2051.47  4850.5 2051.68  4878.4 2045.86  4898.6 2044.17    4929    2039
  4967.1 2028.32  4972.4 2025.67  4972.9 2025.17    4987 2025.67  5002.8 2025.67
  5030.8 2029.43  5058.7 2030.93  5075.5  2034.8  5089.4 2039.37  5103.4 2042.32
  5156.5 2049.21  5192.9  2055.4  5215.2 2057.86    5232  2062.5  5247.1 2065.65
  5259.9 2068.53  5268.3 2071.98  5276.7  2073.8  5304.7 2077.43  5335.4 2079.39
#Mann= 4 ,-1 , 0
  4695.9      .1       0  4972.4     .05       0    4987      .1       0
  5247.1     .07       0
Bank Sta=4972.4,4987
XS Rating Curve= 0 ,0
Exp/Cntr=0.3,0.1

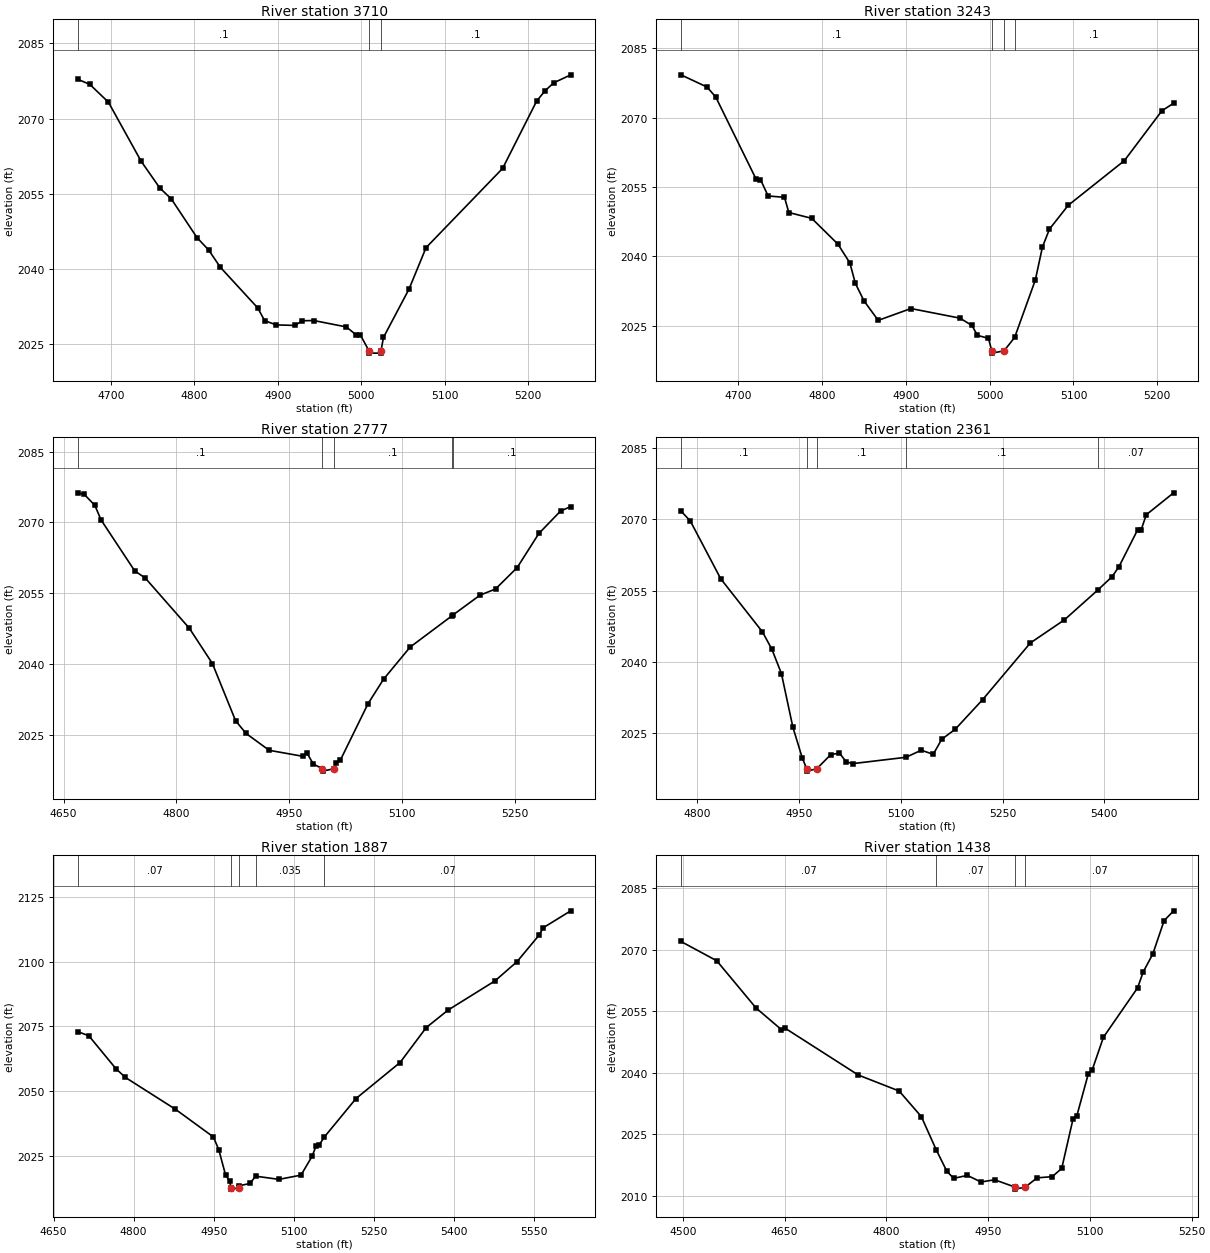
Type RM Length L Ch R = 1 ,3710    ,467,467,467
BEGIN DESCRIPTION:
Indian Creek 01 8.0
END DESCRIPTION:
XS GIS Cut Line= 3
      1795975.04     13941024.98        1795675.       13941175.
        1795425.       13941225.
#Sta/Elev= 30
  4660.5  2077.8  4674.5 2076.83  4696.9 2073.27    4736 2061.53  4758.4 2056.19
  4772.3 2053.98  4803.1 2046.27  4817.1  2043.8    4831 2040.38  4875.8 2032.28
  4884.1 2029.74  4898.1 2028.89  4920.5 2028.79  4928.9 2029.71  4942.8 2029.77
    4982 2028.49  4993.2 2026.98  4998.5 2026.98    5009 2023.77  5009.5 2023.27
  5023.1 2023.27  5023.6 2023.77  5026.5  2026.4  5057.1 2036.02  5077.5 2044.28
  5169.3 2060.08  5210.1  2073.5  5220.3 2075.57  5230.5 2077.12  5250.9 2078.72
#Mann= 3 ,-1 , 0
  4660.5      .1       0    5009     .05       0  5023.6      .1       0
Bank Sta=5009,5023.6
XS Rating Curve= 0 ,0
Exp/Cntr=0.3,0.1

Type RM Length L Ch R = 1 ,3243    ,466,466,466
BEGIN DESCRIPTION:
Indian Creek 01 7.0
END DESCRIPTION:
XS GIS Cut Line= 3
      1795825.02     13940674.99        1795475.       13940775.
      1795275.03     13940874.98
#Sta/Elev= 30
  4631.8 2079.28    4663 2076.63  4673.4 2074.45  4721.5 2056.69  4726.7 2056.61
  4735.8 2053.06  4755.3 2052.77  4760.5 2049.48  4787.8 2048.22    4819 2042.65
  4833.3 2038.57  4839.8 2034.16  4850.2 2030.34  4867.1 2026.14  4906.1  2028.7
  4964.6 2026.62  4978.9 2025.04  4985.4  2022.9  4998.6 2022.25  5002.5 2019.55
    5003 2019.05  5017.2 2019.55  5029.8 2022.44  5054.5 2034.88  5062.9 2041.97
  5071.3 2045.88  5093.7 2051.04  5160.7 2060.71  5205.5 2071.51  5219.4 2073.13
#Mann= 4 ,-1 , 0
  4631.8      .1       0  5002.5     .05       0  5017.2      .1       0
  5029.8      .1       0
Bank Sta=5002.5,5017.2
XS Rating Curve= 0 ,0
Exp/Cntr=0.3,0.1

Type RM Length L Ch R = 1 ,2777    ,416,416,416
BEGIN DESCRIPTION:
Indian Creek 01 6.0
END DESCRIPTION:
XS GIS Cut Line= 3
      1795574.96     13940225.02        1795275.       13940375.
      1795025.02     13940574.99
#Sta/Elev= 30
  4669.2 2076.27  4677.5 2075.93  4691.5 2073.63  4699.9 2070.51  4744.6 2059.74
  4758.6 2058.23  4817.3 2047.59    4848 2040.11  4878.8 2028.01  4892.8 2025.31
  4923.5 2021.75  4968.2 2020.48  4973.8 2021.17  4982.2 2018.85  4994.4 2017.84
  4994.9 2017.34  5009.2 2017.84  5011.8 2018.96  5018.2 2019.66    5055 2031.62
  5075.8 2036.83    5111  2043.6  5166.3 2050.18  5167.5 2050.34  5203.9 2054.59
  5224.7 2055.91  5253.5 2060.45  5282.3 2067.66  5311.1  2072.4  5324.7 2073.37
#Mann= 5 ,-1 , 0
  4669.2      .1       0  4994.4     .05       0  5009.2      .1       0
  5166.3     .07       0  5167.5      .1       0
Bank Sta=4994.4,5009.2
XS Rating Curve= 0 ,0
Exp/Cntr=0.3,0.1

Type RM Length L Ch R = 1 ,2361    ,474,474,474
BEGIN DESCRIPTION:
Indian Creek 01 5.0
END DESCRIPTION:
XS GIS Cut Line= 3
      1795374.98     13939925.01        1795175.       13940025.
      1794674.97       13939975.
#Sta/Elev= 30
    4776 2071.78  4789.9 2069.65  4834.7 2057.48  4896.2 2046.29  4910.1 2042.62
  4924.1 2037.52  4940.9 2026.27  4954.9  2019.7  4961.4 2017.46  4961.9 2016.96
  4976.2 2017.46  4996.8 2020.43  5009.6 2020.77  5019.7 2018.89  5029.7 2018.55
  5107.8 2019.88  5130.2 2021.37  5147.8  2020.5  5160.4 2023.67  5180.5 2025.82
  5220.7 2032.03    5291 2043.97  5341.3 2048.85  5390.1 2055.08  5411.6 2057.96
  5421.7 2060.07  5449.3 2067.87  5454.3 2067.83  5461.9 2070.99  5502.1  2075.6
#Mann= 5 ,-1 , 0
    4776      .1       0  4961.4     .05       0  4976.2      .1       0
  5107.8      .1       0  5390.1     .07       0
Bank Sta=4961.4,4976.2
XS Rating Curve= 0 ,0
Exp/Cntr=0.3,0.1

Type RM Length L Ch R = 1 ,1887    ,449,449,449
BEGIN DESCRIPTION:
Indian Creek 01 4.0
END DESCRIPTION:
XS GIS Cut Line= 3
      1795274.96     13939575.01        1794975.       13939625.
      1794374.96     13939775.01
#Sta/Elev= 30
  4695.9 2072.92  4716.1 2071.35  4766.8 2058.62  4784.6 2055.22  4878.3  2042.9
  4949.3 2032.19  4959.4 2027.27  4972.1 2017.49  4979.7 2015.07  4982.4 2012.48
  4982.9 2011.98  4997.4 2012.48  4997.5 2013.29    5018 2014.16  5028.3    2017
  5072.1 2015.76  5113.4  2017.4    5134 2024.63  5141.7  2028.7  5146.9 2028.89
  5156.9 2032.11  5216.5 2047.07  5298.9    2061  5347.9 2074.53  5389.1 2081.35
  5476.7 2092.62    5518 2100.07  5559.2 2110.32  5566.9 2113.17  5618.5 2119.74
#Mann= 5 ,-1 , 0
  4695.9     .07       0  4982.4     .05       0  4997.4     .07       0
  5028.3    .035       0  5156.9     .07       0
Bank Sta=4982.4,4997.4
XS Rating Curve= 0 ,0
Exp/Cntr=0.3,0.1

Type RM Length L Ch R = 1 ,1438    ,432,432,432
BEGIN DESCRIPTION:
Indian Creek 01 3.0
END DESCRIPTION:
XS GIS Cut Line= 3
      1795225.01       13939225.        1794725.       13939275.
      1794525.01     13939374.99
#Sta/Elev= 30
  4497.2    2072    4550 2067.29  4607.8 2055.79  4645.4 2050.48  4650.5 2050.87
  4758.5 2039.43  4818.8 2035.52  4851.5 2029.28  4873.5 2021.16  4889.2 2015.92
  4899.2 2014.22  4919.3 2014.94  4939.4 2013.33  4959.5 2013.87  4989.6 2012.09
  4990.1 2011.59  5004.7 2012.09  5022.1 2014.34  5044.4 2014.63  5058.4 2016.63
  5075.2 2028.79  5080.8 2029.54  5097.5 2039.67  5103.1 2040.56  5119.9 2048.64
  5170.2 2060.68  5178.6  2064.6  5192.6 2068.92  5209.3 2077.07  5223.3 2079.47
#Mann= 4 ,-1 , 0
  4497.2     .07       0  4873.5     .07       0  4989.6     .05       0
  5004.7     .07       0
Bank Sta=4989.6,5004.7
XS Rating Curve= 0 ,0
Exp/Cntr=0.3,0.1

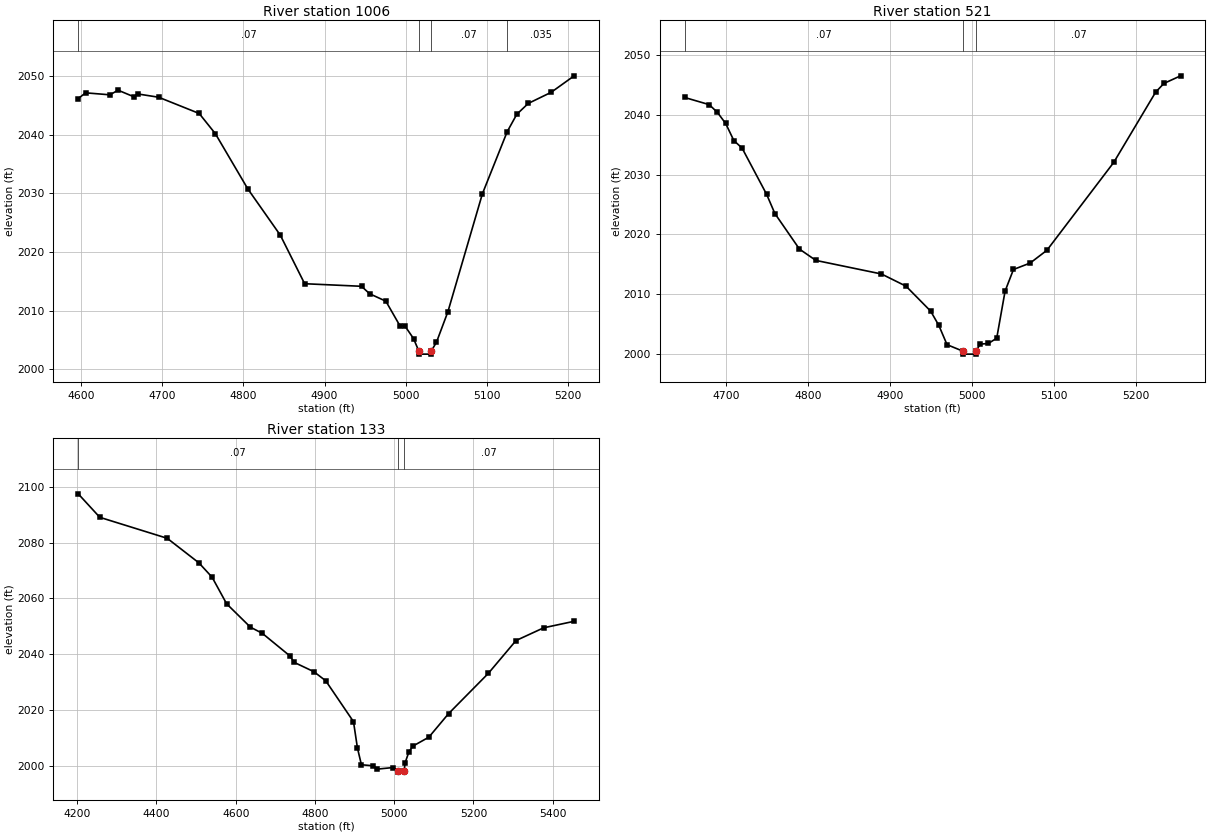
Type RM Length L Ch R = 1 ,1006    ,485,485,485
BEGIN DESCRIPTION:
Indian Creek 01 2.0
END DESCRIPTION:
XS GIS Cut Line= 3
      1795024.11     13938868.89        1794625.       13938875.
        1794475.       13939025.
#Sta/Elev= 30
  4596.3 2046.18  4605.4 2047.16  4635.4 2046.82  4645.4 2047.61  4664.7  2046.5
  4669.7 2046.97  4695.4 2046.41  4745.4 2043.64  4765.4 2040.18  4805.4 2030.76
  4845.4 2022.88  4875.4  2014.6  4945.5 2014.16  4955.5 2012.89  4975.5 2011.62
    4993 2007.39    4999 2007.39  5009.6 2005.25  5016.2 2003.09  5016.7 2002.59
  5030.8 2002.59  5031.3 2003.09  5037.9 2004.62    5052 2009.83  5094.5 2029.94
  5125.1 2040.54  5136.9  2043.5    5151 2045.35  5179.3 2047.25  5207.6 2050.06
#Mann= 4 ,-1 , 0
  4596.3     .07       0  5016.2     .05       0  5031.3     .07       0
  5125.1    .035       0
Bank Sta=5016.2,5031.3
XS Rating Curve= 0 ,0
Exp/Cntr=0.3,0.1

Type RM Length L Ch R = 1 ,521     ,388,388,388
BEGIN DESCRIPTION:
Indian Creek 01 1.0
END DESCRIPTION:
XS GIS Cut Line= 3
      1794874.99       13938425.        1794525.       13938425.
      1794275.05     13938375.01
#Sta/Elev= 30
  4649.9 2042.88  4679.9 2041.68  4689.9 2040.37  4699.9 2038.53  4709.9 2035.67
  4719.9 2034.42  4749.9 2026.67  4759.9 2023.48  4789.9 2017.53  4809.9 2015.64
  4889.9 2013.37  4919.9 2011.33  4949.9 2007.16  4959.9 2004.77  4969.9 2001.55
  4989.2 2000.47  4989.7 1999.97    5005 1999.97  5005.5 2000.47  5010.1 2001.64
  5020.3 2001.75  5030.5 2002.64  5040.7  2010.5  5050.9 2014.12  5071.3  2015.2
  5091.7 2017.33  5173.3 2032.04  5224.3 2043.76  5234.4 2045.23  5254.8  2046.5
#Mann= 3 ,-1 , 0
  4649.9     .07       0  4989.2     .05       0  5005.5     .07       0
Bank Sta=4989.2,5005.5
XS Rating Curve= 0 ,0
Exp/Cntr=0.3,0.1

Type RM Length L Ch R = 1 ,133     ,0,0,0
BEGIN DESCRIPTION:
Indian Creek 01 0.0
END DESCRIPTION:
XS GIS Cut Line= 2
      1795429.53     13938052.48      1794178.24     13938080.49
#Sta/Elev= 30
  4202.5 2097.59    4257 2089.15  4427.1 2081.62  4507.1 2072.79  4540.4 2067.63
  4577.1 2058.08  4637.1 2049.69  4667.1 2047.48  4737.2 2039.31  4747.2 2037.07
  4797.2  2033.7  4827.2 2030.43  4897.2 2015.75  4907.2 2006.27  4917.2 2000.27
  4947.2 1999.89  4957.2  1998.7  4997.2 1999.27  5009.1 1998.12  5009.6 1997.62
  5025.4 1998.12  5027.2 2000.85  5037.2 2004.95  5047.2 2006.98  5087.3 2010.16
  5137.3 2018.65  5237.3 2033.06  5307.3 2044.88  5377.3 2049.47  5454.1  2051.8
#Mann= 3 ,-1 , 0
  4202.5     .07       0  5009.1     .05       0  5025.4     .07       0
Bank Sta=5009.1,5025.4
XS Rating Curve= 0 ,0
Exp/Cntr=0.3,0.1

Chan Stop Cuts=-1
Use User Specified Reach Order=0
Composite Channel Slope=5