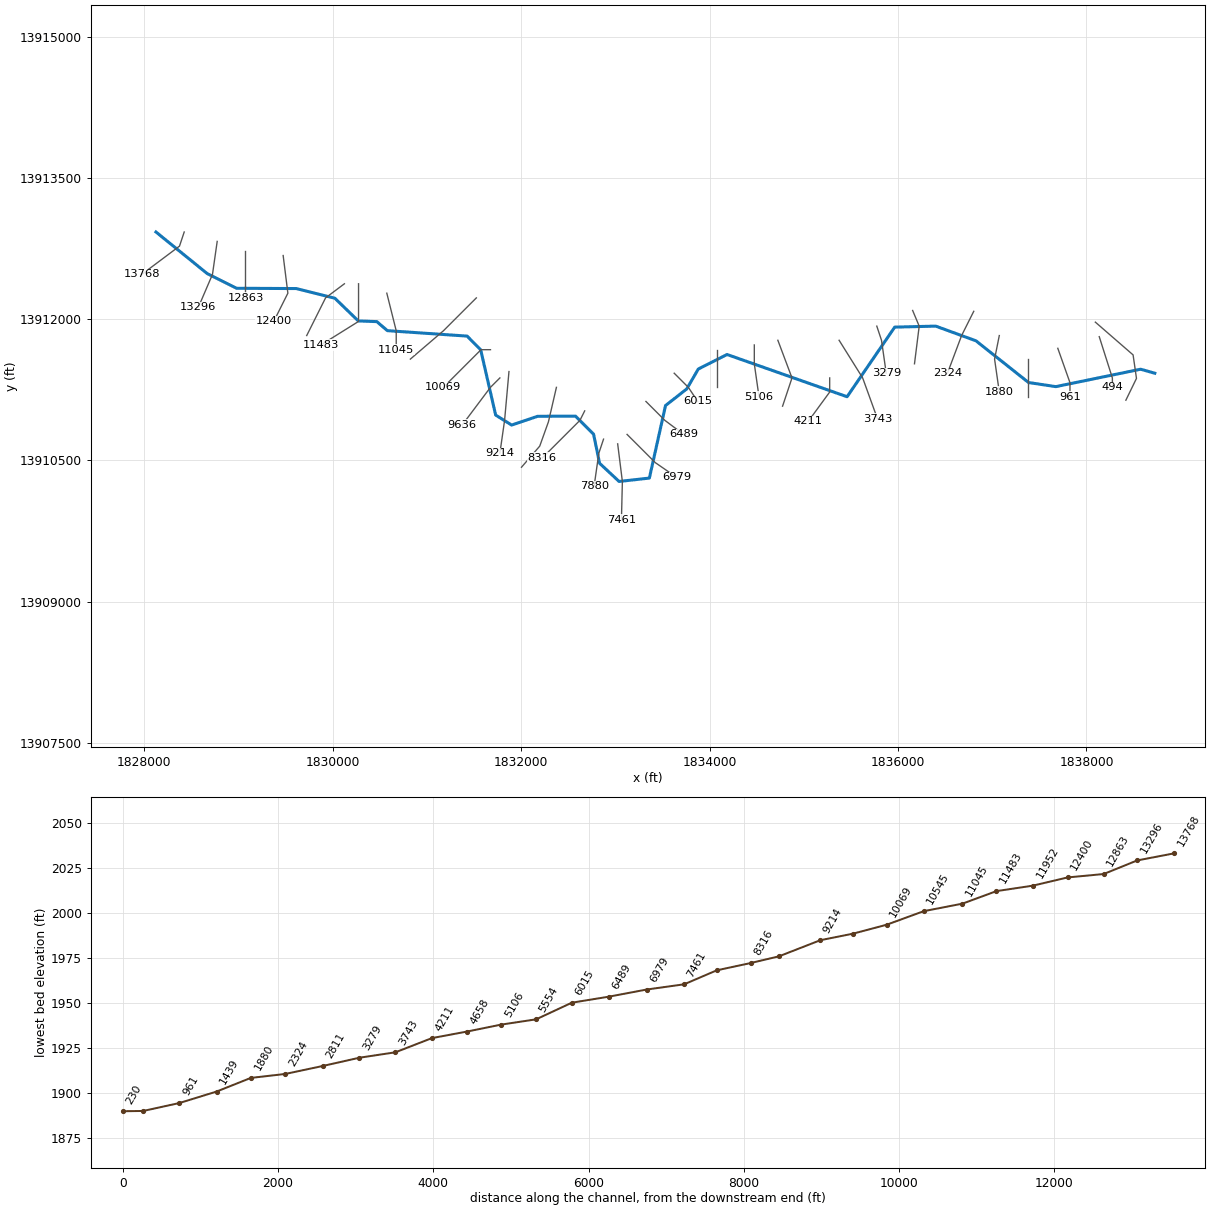
--- Indian Creek 02.prj (project) ---

Proj Title=Indian Creek 02 Base Level Engineering
Current Plan=p01
Default Exp/Contr=0.3,0.1
English Units
Geom File=g01
Flow File=f01
Plan File=p01
BEGIN DESCRIPTION:
Indian Creek 02
END DESCRIPTION:

--- Indian Creek 02.p01 (plan) ---

Plan Title=Multiple Run
Short Identifier=Multiple
Geom File=g01
Flow File=f01
Subcritical Flow
K Sum by GR= 0
Std Step Tol= 0.01
Critical Tol= 0.01
Num of Std Step Trials= 20
Max Error Tol= 0.3
Flow Tol Ratio= 0.001
Split Flow NTrial= 30
Split Flow Tol= 0.02
Split Flow Ratio= 0.02
Log Output Level= 0
Friction Slope Method= 1
Unsteady Friction Slope Method= 2
Unsteady Bridges Friction Slope Method= 1
Parabolic Critical Depth
Global Vel Dist=  1 , 1 , 1
Global Log Level= 0
CheckData=True
Encroach Param= -1, 0, 0, 0
BEGIN DESCRIPTION:
Multiple Run
END DESCRIPTION:

--- Indian Creek 02.f01 (steady flow) ---

Flow Title=Multiple
Number of Profiles=7
Profile Names=10-year,25-year,50-year,1pct_min,100-year,1pct_plu,500-year
River Rch & RM= Indian Creek 02,Reach-1,13768
    2163    3856    5534    3830    7642   15247   14417
River Rch & RM= Indian Creek 02,Reach-1,9214
    2558    4585    6604    4583    9144   18245   17357
River Rch & RM= Indian Creek 02,Reach-1,2324
    3295    5976    8673    6061   12093   24129   23279
Boundary for River Rch & Prof#=Indian Creek 02,Reach-1,1
Up Type=0
Dn Type=3
Dn Slope=0.005
Boundary for River Rch & Prof#=Indian Creek 02,Reach-1,2
Up Type=0
Dn Type=3
Dn Slope=0.005
Boundary for River Rch & Prof#=Indian Creek 02,Reach-1,3
Up Type=0
Dn Type=3
Dn Slope=0.005
Boundary for River Rch & Prof#=Indian Creek 02,Reach-1,4
Up Type=0
Dn Type=3
Dn Slope=0.005
Boundary for River Rch & Prof#=Indian Creek 02,Reach-1,5
Up Type=0
Dn Type=3
Dn Slope=0.005
Boundary for River Rch & Prof#=Indian Creek 02,Reach-1,6
Up Type=0
Dn Type=3
Dn Slope=0.005
Boundary for River Rch & Prof#=Indian Creek 02,Reach-1,7
Up Type=0
Dn Type=3
Dn Slope=0.005

--- Indian Creek 02.g01 (geometry) ---

Geom Title=Existing Conditions

River Reach=Indian Creek 02,Reach-1
Reach XY= 30
      1828125.00     13912925.00      1828668.95     13912483.16
      1828980.85     13912327.07      1829614.29     13912324.18
      1830023.53     13912221.45      1830272.30     13911980.36
      1830469.14     13911972.93      1830580.86     13911877.07
      1831427.30     13911819.17      1831571.39     13911673.50
      1831730.26     13910980.47      1831899.96     13910874.51
      1832175.00     13910967.44      1832577.45     13910969.54
      1832769.53     13910777.45      1832832.86     13910468.83
      1833040.16     13910275.38      1833361.56     13910311.36
      1833532.70     13911081.47      1833758.35     13911258.33
      1833880.62     13911469.38      1834185.55     13911623.90
      1835459.78     13911175.24      1835965.20     13911914.52
      1836400.10     13911925.24      1836827.30     13911769.17
      1837385.50     13911326.20      1837675.00     13911282.56
      1838575.01     13911467.49      1838725.00     13911425.00

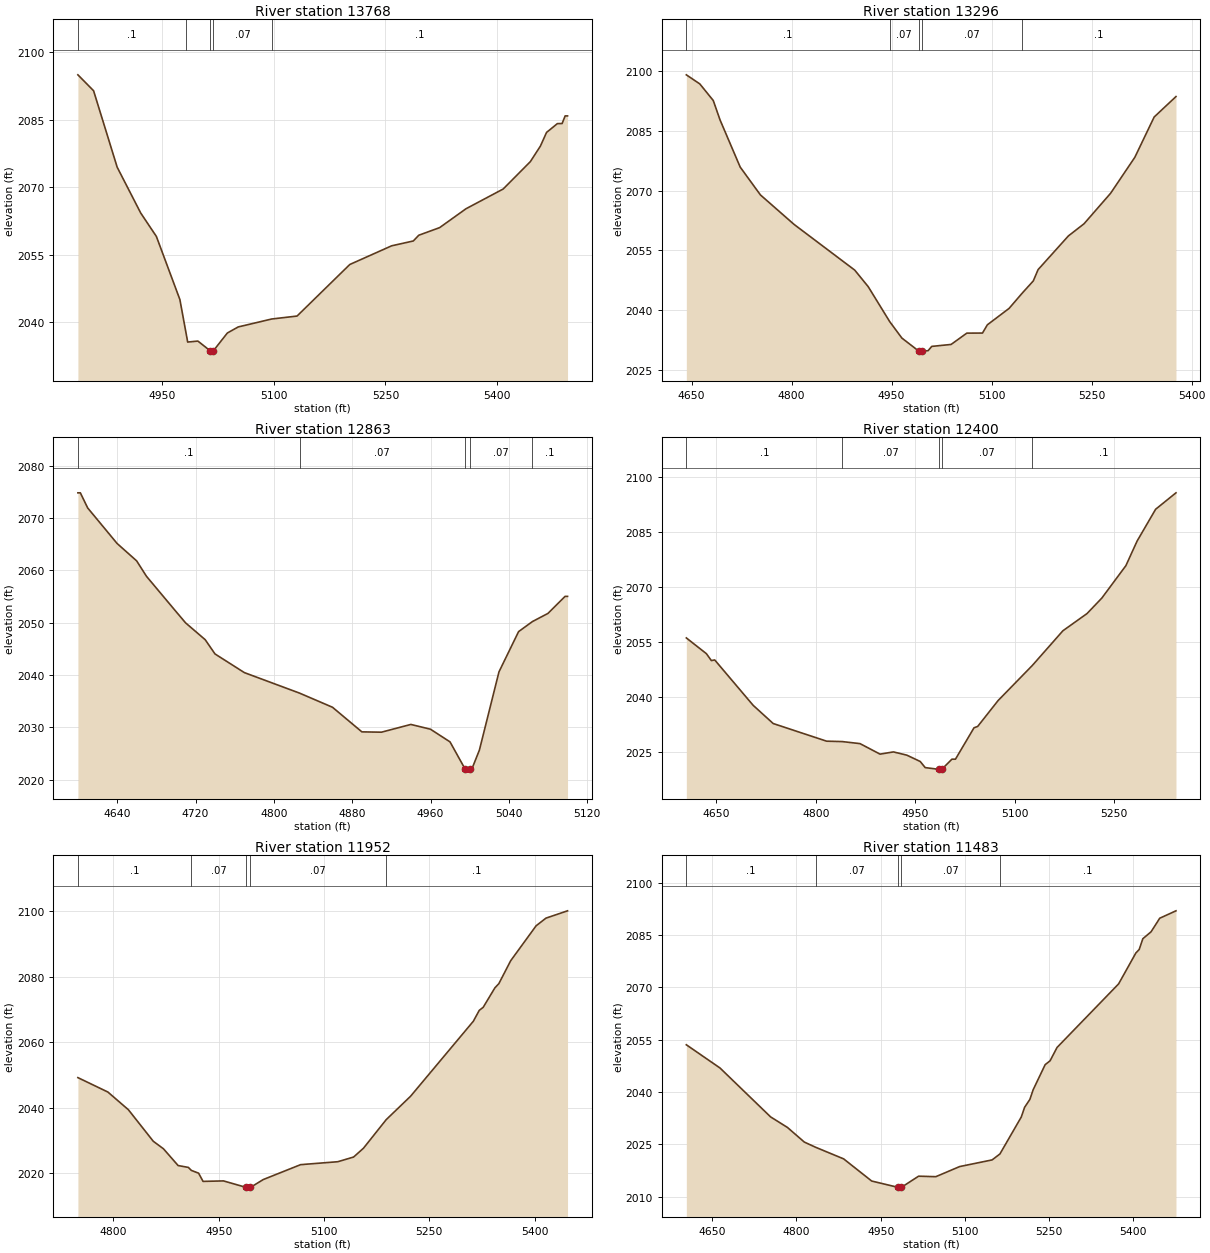
Type RM Length L Ch R = 1,13768,472,472,472
BEGIN DESCRIPTION:
Indian Creek 02 30.0
END DESCRIPTION:
XS GIS Cut Line= 3
      1828425.02     13912925.05      1828375.00     13912775.00
      1827974.97     13912474.98
#Sta/Elev= 30
  4836.6 2094.99  4857.7 2091.45  4889.4 2074.46  4921.0 2064.29  4942.1 2059.07
  4973.7 2045.04  4982.2 2037.39  4984.2 2035.59  4997.9 2035.81  5014.6 2033.63
  5014.9 2033.13  5018.6 2033.63  5037.5 2037.60  5052.1 2038.95  5097.3 2040.72
  5131.2 2041.37  5202.1 2052.83  5258.3 2056.98  5287.5 2058.06  5294.8 2059.33
  5322.9 2061.03  5358.3 2065.22  5408.3 2069.61  5444.8 2075.69  5458.3 2079.14
  5466.6 2082.19  5481.2 2084.15  5487.5 2084.16  5491.6 2085.86  5494.8 2085.86
#Mann=5,-1,0
  4836.6     0.1       0  4982.2    0.07       0  5014.6    0.05       0
  5018.6    0.07       0  5097.3     0.1       0
Bank Sta=5014.6,5018.6
Exp/Cntr=0.3,0.1

Type RM Length L Ch R = 1,13296,433,433,433
BEGIN DESCRIPTION:
Indian Creek 02 29.0
END DESCRIPTION:
XS GIS Cut Line= 3
      1828775.00     13912825.02      1828725.00     13912475.00
      1828574.98     13912124.96
#Sta/Elev= 30
  4642.1 2099.11  4662.3 2096.83  4682.5 2092.66  4692.6 2087.81  4722.9 2075.94
  4753.2 2068.96  4803.7 2061.55  4894.7 2050.07  4914.9 2045.92  4947.1 2037.15
  4965.4 2033.01  4990.8 2029.73  4991.1 2029.23  4995.5 2029.73  5004.7 2029.84
  5010.2 2030.92  5039.2 2031.41  5062.8 2034.25  5086.3 2034.27  5093.6 2036.34
  5126.2 2040.46  5145.5 2044.22  5162.5 2047.36  5169.7 2050.20  5215.1 2058.65
  5238.6 2061.71  5278.5 2069.38  5314.8 2078.40  5343.8 2088.52  5376.5 2093.65
#Mann=5,-1,0
  4642.1     0.1       0  4947.1    0.07       0  4990.8    0.05       0
  4995.5    0.07       0  5145.5     0.1       0
Bank Sta=4990.8,4995.5
Exp/Cntr=0.3,0.1

Type RM Length L Ch R = 1,12863,463,463,463
BEGIN DESCRIPTION:
Indian Creek 02 28.0
END DESCRIPTION:
XS GIS Cut Line= 3
      1829075.00     13912725.01      1829075.00     13912325.00
      1829075.00     13912225.01
#Sta/Elev= 30
  4599.9 2074.83  4602.4 2074.83  4609.9 2071.94  4639.9 2065.16  4659.9 2061.83
  4669.9 2058.89  4699.9 2052.19  4709.9 2049.98  4729.9 2046.77  4739.9 2044.05
  4769.9 2040.48  4826.3 2036.56  4859.9 2033.86  4889.9 2029.16  4909.9 2029.10
  4939.9 2030.58  4959.9 2029.67  4979.9 2027.25  4995.0 2022.16  4995.4 2021.66
  4999.5 2021.66  4999.8 2022.16  5002.4 2022.16  5009.9 2025.68  5029.9 2040.63
  5049.9 2048.31  5064.0 2050.23  5079.9 2051.79  5097.4 2055.05  5099.9 2055.05
#Mann=5,-1,0
  4599.9     0.1       0  4826.3    0.07       0  4995.0    0.05       0
  4999.8    0.07       0  5064.0     0.1       0
Bank Sta=4995,4999.8
Exp/Cntr=0.3,0.1

Type RM Length L Ch R = 1,12400,448,448,448
BEGIN DESCRIPTION:
Indian Creek 02 27.0
END DESCRIPTION:
XS GIS Cut Line= 3
      1829475.00     13912674.99      1829525.00     13912275.00
      1829375.01     13911975.01
#Sta/Elev= 30
  4604.7 2056.16  4634.9 2051.87  4642.5 2049.97  4647.5 2050.15  4705.5 2037.75
  4735.7 2032.78  4816.3 2027.96  4839.8 2027.85  4866.7 2027.29  4896.9 2024.42
  4917.1 2025.03  4937.3 2024.14  4957.4 2022.42  4965.0 2020.74  4985.2 2020.28
  4985.6 2019.78  4990.0 2020.28  5005.3 2023.04  5010.6 2023.04  5038.6 2031.62
  5044.1 2031.98  5074.9 2039.05  5126.5 2048.63  5172.7 2058.12  5209.1 2062.82
  5231.4 2067.05  5267.7 2075.91  5284.5 2082.59  5312.5 2091.30  5343.2 2095.79
#Mann=5,-1,0
  4604.7     0.1       0  4839.8    0.07       0  4985.2    0.05       0
  4990.0    0.07       0  5126.5     0.1       0
Bank Sta=4985.2,4990
Exp/Cntr=0.3,0.1

Type RM Length L Ch R = 1,11952,469,469,469
BEGIN DESCRIPTION:
Indian Creek 02 26.0
END DESCRIPTION:
XS GIS Cut Line= 3
      1830125.03     13912375.02      1829925.00     13912225.00
      1829725.02     13911825.04
#Sta/Elev= 30
  4749.6 2049.25  4792.3 2044.85  4821.5 2039.45  4856.9 2029.83  4871.5 2027.51
  4892.3 2022.41  4906.9 2021.84  4911.2 2020.92  4921.5 2020.08  4927.8 2017.57
  4956.9 2017.72  4989.6 2015.71  4990.0 2015.21  4995.1 2015.71  5013.6 2018.14
  5066.7 2022.68  5119.8 2023.58  5142.2 2025.01  5156.2 2027.69  5188.6 2036.42
  5223.2 2043.54  5312.7 2066.47  5321.1 2069.78  5326.7 2070.71  5343.4 2076.67
  5349.0 2077.94  5365.8 2084.92  5402.1 2095.61  5416.1 2097.94  5446.8 2100.17
#Mann=5,-1,0
  4749.6     0.1       0  4911.2    0.07       0  4989.6    0.05       0
  4995.1    0.07       0  5188.6     0.1       0
Bank Sta=4989.6,4995.1
Exp/Cntr=0.3,0.1

Type RM Length L Ch R = 1,11483,438,438,438
BEGIN DESCRIPTION:
Indian Creek 02 25.0
END DESCRIPTION:
XS GIS Cut Line= 3
      1830275.00     13912374.95      1830275.00     13911975.00
      1829874.96     13911724.98
#Sta/Elev= 30
  4604.1 2053.57  4664.1 2046.90  4754.1 2032.89  4784.1 2029.86  4814.1 2025.67
  4834.2 2024.18  4884.1 2020.85  4934.1 2014.49  4981.3 2012.67  4981.7 2012.17
  4986.8 2012.67  5017.6 2015.88  5048.3 2015.74  5090.7 2018.64  5148.5 2020.55
  5162.4 2022.26  5200.4 2032.85  5206.3 2035.63  5215.7 2037.90  5221.6 2040.69
  5242.9 2047.86  5251.7 2048.98  5264.1 2052.80  5373.7 2071.03  5404.4 2079.89
  5410.3 2080.88  5416.8 2083.98  5431.5 2085.97  5446.9 2089.86  5475.8 2091.98
#Mann=5,-1,0
  4604.1     0.1       0  4834.2    0.07       0  4981.3    0.05       0
  4986.8    0.07       0  5162.4     0.1       0
Bank Sta=4981.3,4986.8
Exp/Cntr=0.3,0.1

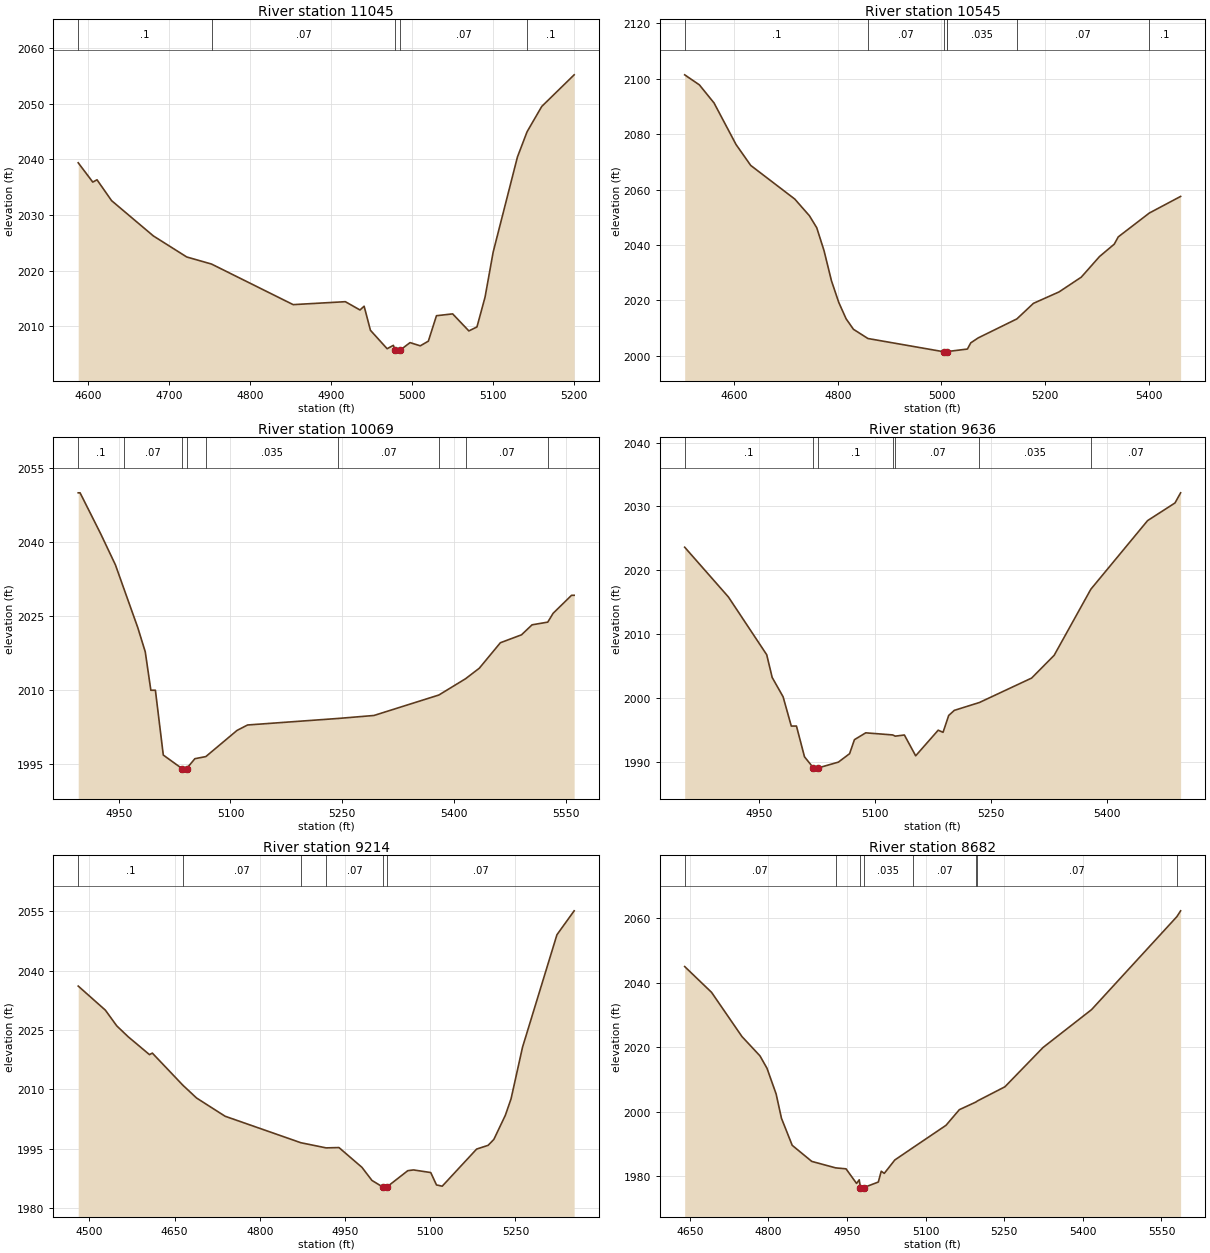
Type RM Length L Ch R = 1,11045,500,500,500
BEGIN DESCRIPTION:
Indian Creek 02 24.0
END DESCRIPTION:
XS GIS Cut Line= 3
      1830575.00     13912274.99      1830675.00     13911875.00
      1830675.00     13911675.00
#Sta/Elev= 30
  4587.6 2039.40  4605.6 2035.93  4610.8 2036.35  4628.8 2032.60  4680.4 2026.26
  4721.6 2022.48  4752.2 2021.21  4853.0 2013.92  4917.4 2014.45  4935.5 2012.96
  4940.6 2013.64  4948.4 2009.31  4969.0 2006.00  4976.7 2006.61  4979.0 2005.71
  4979.5 2005.21  4984.7 2005.71  4997.3 2007.10  5009.9 2006.52  5019.9 2007.36
  5029.9 2011.93  5049.9 2012.26  5069.9 2009.20  5079.9 2009.91  5089.9 2015.27
  5099.9 2023.35  5129.9 2040.45  5141.8 2044.98  5159.9 2049.52  5199.9 2055.20
#Mann=5,-1,0
  4587.6     0.1       0  4752.2    0.07       0  4979.0    0.05       0
  4984.7    0.07       0  5141.8     0.1       0
Bank Sta=4979,4984.7
Exp/Cntr=0.3,0.1

Type RM Length L Ch R = 1,10545,476,476,476
BEGIN DESCRIPTION:
Indian Creek 02 23.0
END DESCRIPTION:
XS GIS Cut Line= 3
      1831525.03     13912225.03      1831175.00     13911875.00
      1830825.00     13911575.00
#Sta/Elev= 30
  4505.0 2101.35  4533.3 2097.74  4561.6 2091.21  4604.0 2076.23  4632.3 2068.69
  4717.2 2056.56  4745.5 2050.53  4759.6 2046.21  4773.7 2037.91  4787.9 2027.12
  4802.0 2019.31  4816.2 2013.38  4830.3 2009.61  4858.2 2006.28  5004.2 2001.51
  5004.7 2001.01  5010.1 2001.51  5010.4 2001.56  5050.0 2002.48  5056.5 2004.72
  5070.8 2006.50  5145.4 2013.35  5177.3 2018.96  5226.7 2023.08  5269.5 2028.40
  5304.6 2035.82  5333.1 2040.31  5340.8 2042.92  5400.6 2051.51  5461.0 2057.51
#Mann=7,-1,0
  4505.0     0.1       0  4858.2    0.07       0  5004.2    0.05       0
  5010.1    0.07       0  5010.4   0.035       0  5145.4    0.07       0
  5400.6     0.1       0
Bank Sta=5004.2,5010.1
Exp/Cntr=0.3,0.1

Type RM Length L Ch R = 1,10069,433,433,433
BEGIN DESCRIPTION:
Indian Creek 02 22.0
END DESCRIPTION:
XS GIS Cut Line= 3
      1831675.04     13911675.00      1831575.00     13911675.00
      1831175.02     13911275.02
#Sta/Elev= 30
  4895.6 2049.95  4898.1 2049.95  4925.6 2041.69  4945.6 2035.32  4956.5 2030.68
  4975.6 2022.59  4985.6 2017.69  4993.1 2009.90  4999.2 2009.90  5009.8 1996.75
  5035.1 1993.99  5035.6 1993.49  5040.6 1993.49  5041.0 1993.99  5052.2 1996.01
  5066.9 1996.44  5108.8 2001.75  5122.9 2002.85  5244.8 2004.18  5292.6 2004.78
  5379.7 2008.93  5415.5 2012.23  5434.0 2014.37  5462.3 2019.54  5490.6 2021.14
  5504.8 2023.17  5525.9 2023.72  5533.0 2025.50  5557.8 2029.16  5561.3 2029.16
#Mann=9,-1,0
  4895.6     0.1       0  4956.5    0.07       0  5035.1    0.05       0
  5041.0    0.07       0  5066.9   0.035       0  5244.8    0.07       0
  5379.7   0.035       0  5415.5    0.07       0  5525.9   0.035       0
Bank Sta=5035.1,5041
Exp/Cntr=0.3,0.1

Type RM Length L Ch R = 1,9636,422,422,422
BEGIN DESCRIPTION:
Indian Creek 02 21.0
END DESCRIPTION:
XS GIS Cut Line= 3
      1831775.03     13911375.03      1831675.00     13911275.00
      1831374.98     13910874.97
#Sta/Elev= 30
  4853.6 2023.61  4910.2 2015.81  4959.7 2006.77  4966.8 2003.20  4980.9 2000.18
  4991.5 1995.59  4998.2 1995.59  5008.6 1990.77  5020.2 1989.03  5020.7 1988.53
  5026.2 1989.03  5052.4 1989.94  5066.9 1991.26  5073.2 1993.46  5087.8 1994.53
  5122.6 1994.20  5126.0 1994.01  5137.8 1994.19  5152.4 1990.93  5181.5 1994.94
  5187.8 1994.61  5195.1 1997.25  5202.4 1998.05  5234.8 1999.28  5302.4 2003.11
  5331.5 2006.67  5379.0 2017.03  5452.4 2027.78  5487.8 2030.54  5495.1 2032.13
#Mann=7,-1,0
  4853.6     0.1       0  5020.2    0.05       0  5026.2     0.1       0
  5122.6   0.035       0  5126.0    0.07       0  5234.8   0.035       0
  5379.0    0.07       0
Bank Sta=5020.2,5026.2
Exp/Cntr=0.3,0.1

Type RM Length L Ch R = 1,9214,532,532,532
BEGIN DESCRIPTION:
Indian Creek 02 20.0
END DESCRIPTION:
XS GIS Cut Line= 3
      1831871.43     13911442.59      1831825.00     13910925.00
      1831775.00     13910575.02
#Sta/Elev= 30
  4480.2 2036.08  4528.0 2030.01  4548.1 2026.04  4568.1 2023.31  4605.7 2018.79
  4610.7 2019.18  4664.4 2011.09  4688.6 2007.85  4738.8 2003.26  4872.2 1996.58
  4916.7 1995.28  4939.3 1995.36  4979.8 1990.37  4997.4 1987.07  5016.8 1985.38
  5017.3 1984.88  5023.3 1985.38  5060.5 1989.53  5070.6 1989.72  5100.9 1989.06
  5111.0 1985.94  5121.1 1985.62  5181.7 1994.98  5201.9 1995.92  5212.0 1997.41
  5232.2 2003.48  5242.3 2007.65  5262.5 2020.66  5323.1 2049.02  5353.4 2055.05
#Mann=6,-1,0
  4480.2     0.1       0  4664.4    0.07       0  4872.2   0.035       0
  4916.7    0.07       0  5016.8    0.05       0  5023.3    0.07       0
Bank Sta=5016.8,5023.3
Exp/Cntr=0.3,0.1

Type RM Length L Ch R = 1,8682,366,366,366
BEGIN DESCRIPTION:
Indian Creek 02 19.0
END DESCRIPTION:
XS GIS Cut Line= 4
      1832374.99     13911274.96      1832290.31     13910908.98
      1832198.01     13910651.03      1832004.11     13910426.35
#Sta/Elev= 30
  4640.2 2045.03  4691.5 2037.02  4749.5 2023.30  4783.9 2017.30  4797.3 2013.44
  4814.7 2005.48  4824.9 1997.93  4845.4 1989.53  4882.7 1984.54  4928.2 1982.53
  4948.1 1982.23  4968.2 1977.70  4973.3 1978.82  4975.5 1976.43  4976.0 1975.93
  4982.2 1976.43  5009.7 1978.13  5015.3 1981.49  5021.1 1980.82  5041.2 1984.98
  5075.5 1988.77  5138.9 1995.74  5164.3 2000.59  5196.2 2002.99  5198.8 2003.30
  5251.3 2007.70  5324.2 2019.92  5416.7 2031.66  5579.6 2060.55  5586.6 2062.33
#Mann=8,-1,0
  4640.2    0.07       0  4928.2   0.035       0  4975.5   0.035       0
  4982.2   0.035       0  5075.5    0.07       0  5196.2   0.035       0
  5198.8    0.07       0  5579.6     0.1       0
Bank Sta=4975.5,4982.2
Exp/Cntr=0.3,0.1

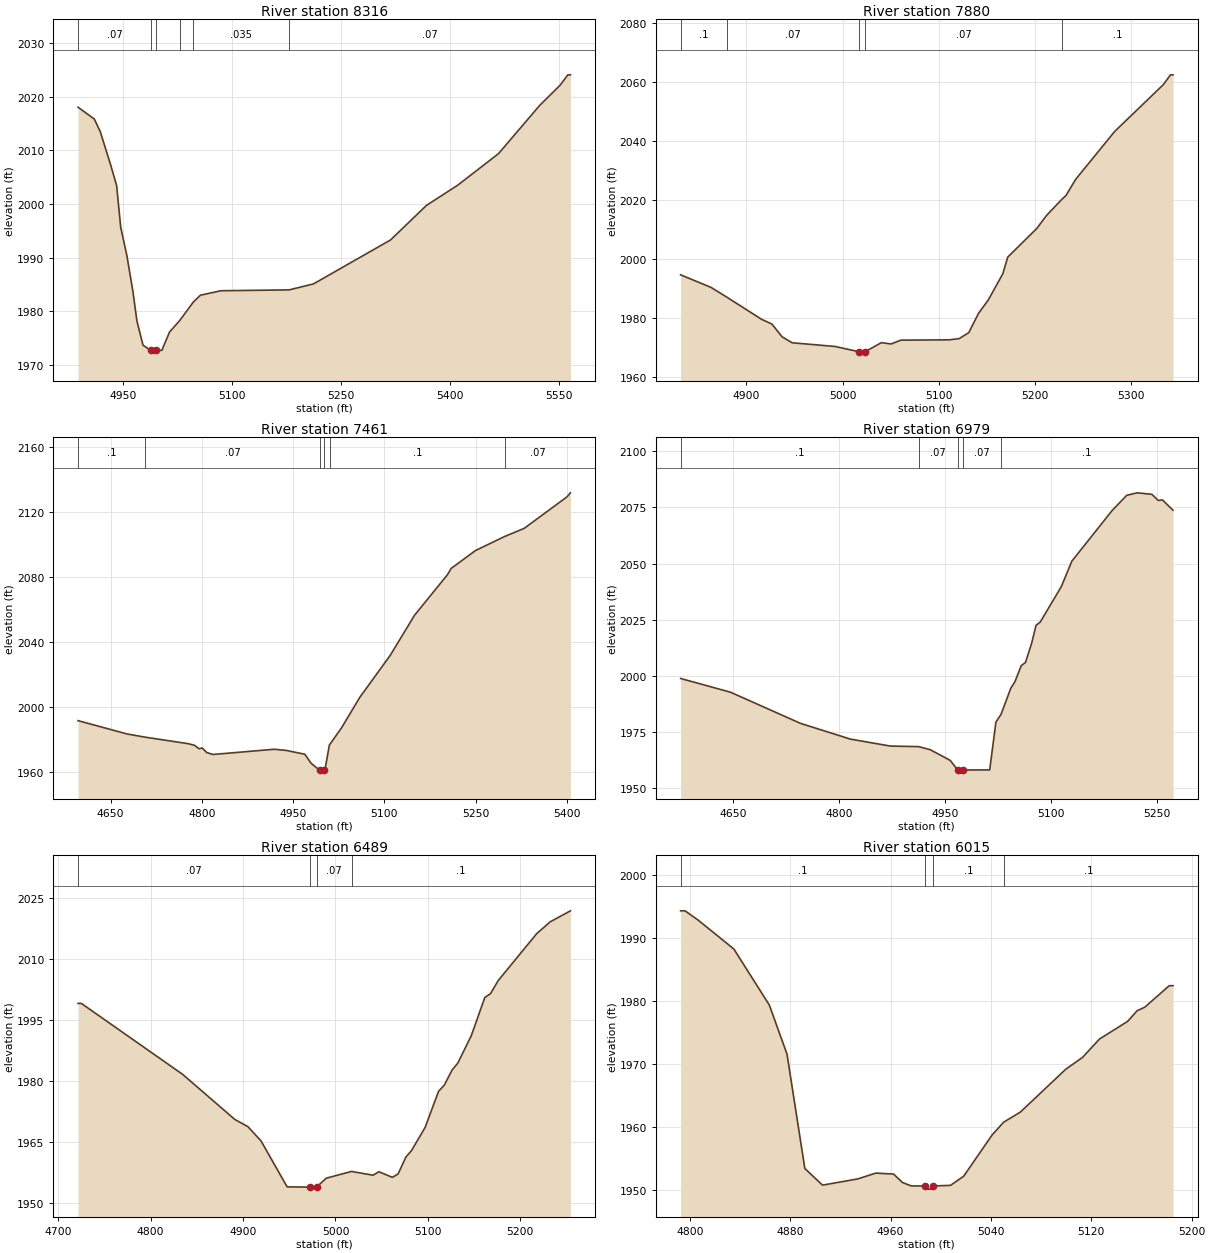
Type RM Length L Ch R = 1,8316,436,436,436
BEGIN DESCRIPTION:
Indian Creek 02 18.0
END DESCRIPTION:
XS GIS Cut Line= 3
      1832675.00     13911024.99      1832625.00     13910925.00
      1832224.99     13910524.99
#Sta/Elev= 30
  4888.5 2018.03  4910.9 2015.83  4919.2 2013.43  4933.2 2007.36  4941.6 2003.43
  4947.2 1995.68  4955.6 1990.45  4964.0 1983.72  4969.5 1978.20  4977.9 1973.67
  4988.6 1972.69  4989.1 1972.19  4994.8 1972.19  4995.3 1972.69  5003.8 1972.71
  5014.4 1976.13  5028.3 1978.25  5047.2 1981.72  5056.9 1982.99  5085.1 1983.82
  5179.0 1983.98  5212.4 1985.09  5318.5 1993.29  5368.0 1999.74  5410.4 2003.45
  5467.0 2009.37  5523.6 2018.36  5551.8 2022.14  5562.4 2024.07  5566.0 2024.07
#Mann=6,-1,0
  4888.5    0.07       0  4988.6    0.05       0  4995.3    0.07       0
  5028.3     0.1       0  5047.2   0.035       0  5179.0    0.07       0
Bank Sta=4988.6,4995.3
Exp/Cntr=0.3,0.1

Type RM Length L Ch R = 1,7880,419,419,419
BEGIN DESCRIPTION:
Indian Creek 02 17.0
END DESCRIPTION:
XS GIS Cut Line= 3
      1832875.00     13910724.99      1832825.00     13910575.00
      1832774.99     13910224.96
#Sta/Elev= 30
  4831.7 1994.70  4863.3 1990.44  4879.4 1987.20  4916.0 1979.59  4926.6 1978.01
  4937.1 1973.69  4947.6 1971.66  4992.3 1970.41  5016.7 1968.65  5017.2 1968.15
  5023.6 1968.65  5040.3 1971.70  5050.4 1971.26  5060.5 1972.55  5111.0 1972.66
  5121.1 1973.06  5131.2 1975.11  5141.3 1981.65  5151.4 1986.15  5166.6 1995.10
  5171.6 2000.69  5201.9 2010.45  5212.0 2014.85  5227.9 2020.31  5232.2 2021.61
  5242.3 2027.11  5282.8 2043.33  5333.3 2059.18  5340.8 2062.52  5343.4 2062.52
#Mann=5,-1,0
  4831.7     0.1       0  4879.4    0.07       0  5016.7    0.05       0
  5023.6    0.07       0  5227.9     0.1       0
Bank Sta=5016.7,5023.6
Exp/Cntr=0.3,0.1

Type RM Length L Ch R = 1,7461,482,482,482
BEGIN DESCRIPTION:
Indian Creek 02 16.0
END DESCRIPTION:
XS GIS Cut Line= 3
      1833025.00     13910674.96      1833075.00     13910275.00
      1833065.01     13909869.00
#Sta/Elev= 30
  4596.5 1991.48  4677.1 1983.27  4707.1 1981.29  4777.9 1977.27  4787.9 1976.28
  4795.5 1974.17  4800.5 1974.64  4808.1 1971.83  4818.2 1970.64  4919.0 1973.86
  4939.1 1973.11  4969.3 1970.78  4979.4 1965.28  4993.6 1960.89  4994.1 1960.39
  5000.5 1960.89  5002.1 1960.89  5009.6 1976.53  5011.2 1977.31  5029.6 1987.09
  5059.6 2005.86  5109.6 2031.71  5149.6 2056.43  5203.7 2081.38  5209.6 2085.18
  5249.7 2096.23  5297.6 2104.88  5329.7 2109.88  5399.7 2129.18  5405.7 2131.76
#Mann=6,-1,0
  4596.5     0.1       0  4707.1    0.07       0  4993.6    0.05       0
  5000.5    0.07       0  5011.2     0.1       0  5297.6    0.07       0
Bank Sta=4993.6,5000.5
Exp/Cntr=0.3,0.1

Type RM Length L Ch R = 1,6979,490,490,490
BEGIN DESCRIPTION:
Indian Creek 02 15.0
END DESCRIPTION:
XS GIS Cut Line= 3
      1833125.02     13910774.98      1833425.00     13910475.00
      1833649.63     13910319.73
#Sta/Elev= 30
  4575.3 1998.77  4646.0 1992.65  4745.0 1978.78  4815.7 1971.76  4872.3 1968.66
  4912.3 1968.41  4928.8 1967.04  4957.1 1962.27  4967.7 1957.99  4968.2 1957.49
  4974.7 1957.99  5013.0 1958.03  5021.8 1979.37  5029.0 1982.74  5042.8 1994.35
  5048.9 1997.46  5057.7 2004.50  5063.7 2005.91  5072.5 2014.58  5078.6 2022.45
  5084.7 2023.96  5114.4 2039.70  5129.3 2051.03  5186.1 2073.51  5207.0 2080.38
  5221.9 2081.49  5242.8 2080.81  5251.6 2078.09  5257.7 2078.32  5272.6 2073.73
#Mann=5,-1,0
  4575.3     0.1       0  4912.3    0.07       0  4967.7    0.05       0
  4974.7    0.07       0  5029.0     0.1       0
Bank Sta=4967.7,4974.7
Exp/Cntr=0.3,0.1

Type RM Length L Ch R = 1,6489,474,474,474
BEGIN DESCRIPTION:
Indian Creek 02 14.0
END DESCRIPTION:
XS GIS Cut Line= 3
      1833324.97     13911125.03      1833525.00     13910925.00
      1833725.01     13910774.99
#Sta/Elev= 30
  4721.4 1999.08  4725.0 1999.08  4834.6 1981.67  4891.1 1970.60  4905.3 1968.82
  4919.4 1965.34  4947.7 1954.06  4972.5 1954.00  4973.0 1953.50  4979.5 1954.00
  4990.1 1956.19  5017.4 1957.84  5040.7 1956.92  5047.0 1957.77  5061.6 1956.39
  5067.8 1957.23  5076.2 1961.36  5082.4 1963.00  5097.0 1968.63  5111.6 1977.51
  5117.8 1979.03  5126.2 1982.72  5132.4 1984.42  5147.0 1991.16  5161.6 2000.52
  5167.8 2001.48  5176.2 2004.71  5217.8 2016.20  5232.4 2019.10  5254.3 2021.80
#Mann=4,-1,0
  4721.4    0.07       0  4972.5    0.05       0  4979.5    0.07       0
  5017.4     0.1       0
Bank Sta=4972.5,4979.5
Exp/Cntr=0.3,0.1

Type RM Length L Ch R = 1,6015,461,461,461
BEGIN DESCRIPTION:
Indian Creek 02 13.0
END DESCRIPTION:
XS GIS Cut Line= 3
      1833625.02     13911424.98      1833775.00     13911275.00
      1833875.01     13911124.99
#Sta/Elev= 30
  4792.7 1994.31  4796.2 1994.31  4806.8 1992.82  4835.1 1988.26  4863.4 1979.37
  4877.5 1971.58  4891.7 1953.45  4905.8 1950.81  4934.1 1951.81  4948.2 1952.72
  4962.4 1952.57  4969.5 1951.23  4976.5 1950.69  4987.1 1950.68  4987.6 1950.18
  4993.7 1950.18  4994.2 1950.68  5007.8 1950.78  5018.3 1952.23  5040.9 1958.76
  5050.1 1960.79  5063.4 1962.39  5099.5 1969.17  5113.0 1971.07  5126.5 1973.98
  5149.0 1976.79  5156.5 1978.47  5162.6 1979.03  5182.1 1982.44  5185.1 1982.44
#Mann=4,-1,0
  4792.7     0.1       0  4987.1    0.05       0  4994.2     0.1       0
  5050.1     0.1       0
Bank Sta=4987.1,4994.2
Exp/Cntr=0.3,0.1

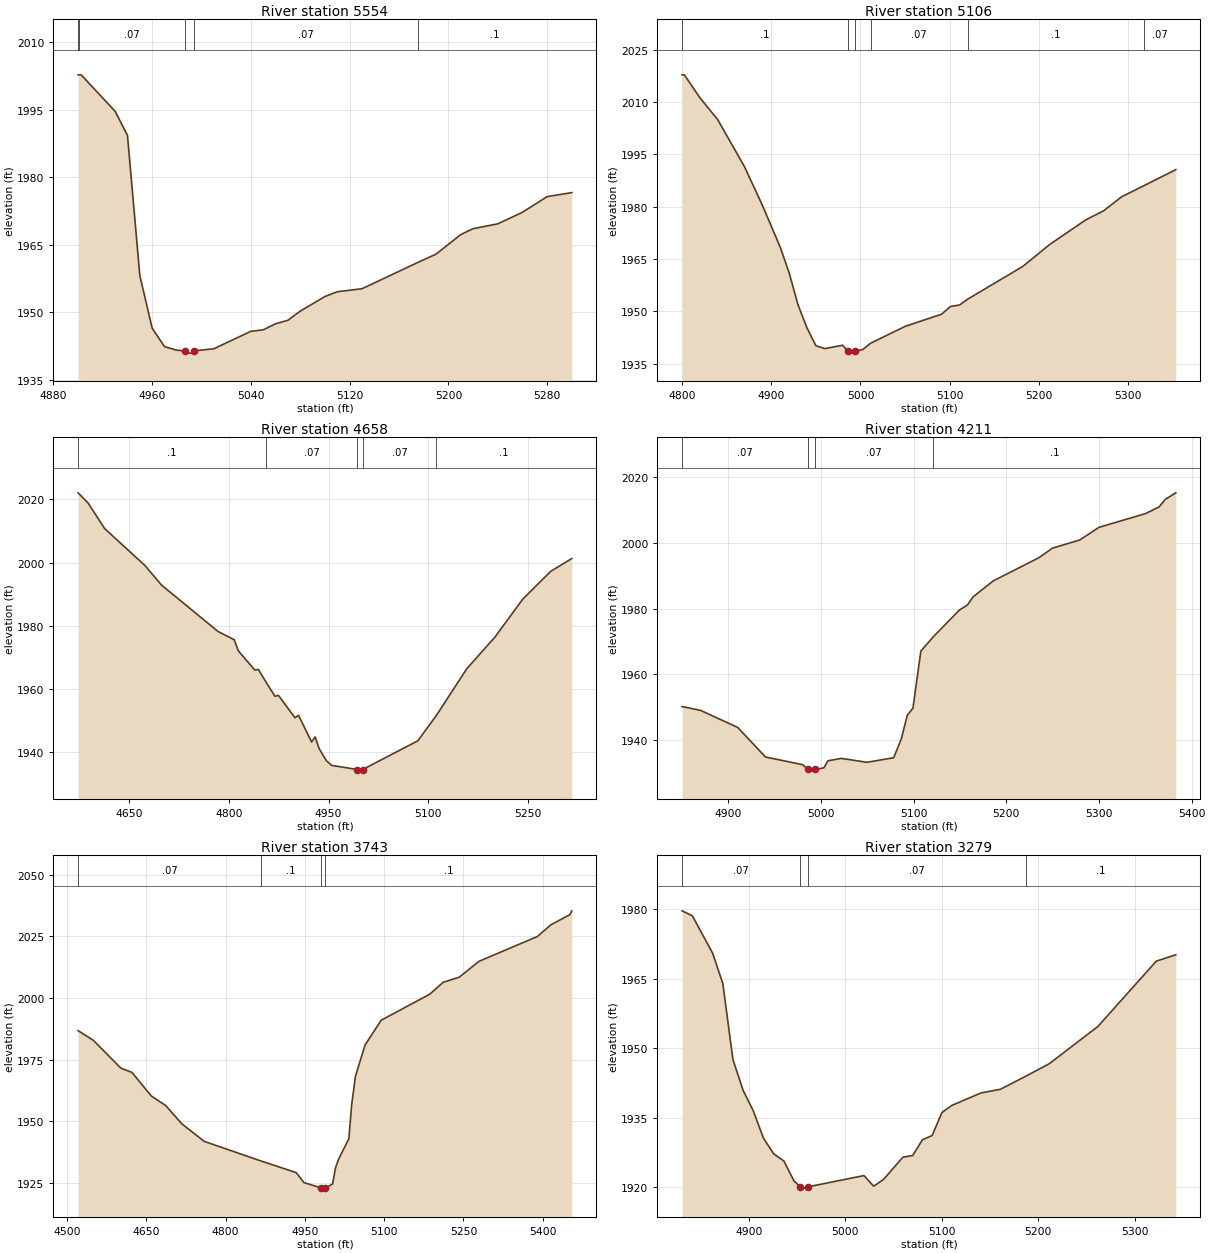
Type RM Length L Ch R = 1,5554,448,448,448
BEGIN DESCRIPTION:
Indian Creek 02 12.0
END DESCRIPTION:
XS GIS Cut Line= 3
      1834075.00     13911675.04      1834075.00     13911575.00
      1834075.00     13911275.04
#Sta/Elev= 30
  4900.0 2002.77  4900.8 2002.77  4902.5 2002.77  4930.0 1994.66  4940.0 1989.32
  4950.0 1958.18  4960.0 1946.48  4970.0 1942.36  4980.0 1941.57  4986.3 1941.42
  4986.8 1940.92  4993.3 1940.92  4993.8 1941.42  5010.0 1941.89  5040.0 1945.77
  5050.0 1946.10  5060.0 1947.44  5070.0 1948.22  5080.0 1950.26  5100.0 1953.50
  5110.0 1954.56  5130.0 1955.23  5175.3 1961.08  5190.0 1962.92  5210.0 1967.26
  5220.0 1968.58  5240.0 1969.65  5260.0 1972.22  5280.0 1975.70  5300.0 1976.59
#Mann=5,-1,0
  4900.0     0.1       0  4900.8    0.07       0  4986.3    0.05       0
  4993.8    0.07       0  5175.3     0.1       0
Bank Sta=4986.3,4993.8
Exp/Cntr=0.3,0.1

Type RM Length L Ch R = 1,5106,448,448,448
BEGIN DESCRIPTION:
Indian Creek 02 11.0
END DESCRIPTION:
XS GIS Cut Line= 3
      1834475.00     13911725.00      1834475.00     13911525.00
      1834525.01     13911174.95
#Sta/Elev= 30
  4800.0 2017.76  4802.5 2017.76  4820.0 2011.18  4840.0 2004.89  4870.0 1991.41
  4890.0 1980.38  4910.0 1968.38  4920.0 1961.04  4930.0 1951.82  4940.0 1945.26
  4950.0 1940.13  4960.0 1939.29  4980.0 1940.27  4986.1 1938.50  4986.6 1938.00
  4993.9 1938.50  5002.5 1939.02  5011.4 1940.84  5050.5 1945.71  5090.9 1949.15
  5101.0 1951.38  5111.1 1951.79  5120.5 1953.51  5181.8 1962.81  5212.1 1969.12
  5252.5 1976.17  5272.7 1978.80  5292.9 1982.82  5318.0 1986.01  5353.6 1990.59
#Mann=6,-1,0
  4800.0     0.1       0  4986.1    0.05       0  4993.9     0.1       0
  5011.4    0.07       0  5120.5     0.1       0  5318.0    0.07       0
Bank Sta=4986.1,4993.9
Exp/Cntr=0.3,0.1

Type RM Length L Ch R = 1,4658,447,447,447
BEGIN DESCRIPTION:
Indian Creek 02 10.0
END DESCRIPTION:
XS GIS Cut Line= 3
      1834725.00     13911775.00      1834875.00     13911375.00
      1834775.01     13911075.03
#Sta/Elev= 30
  4572.8 2022.02  4587.9 2018.80  4612.8 2010.71  4673.4 1999.07  4698.3 1992.89
  4783.7 1978.18  4807.8 1975.62  4814.0 1972.11  4838.9 1966.01  4844.2 1966.22
  4856.3 1962.05  4869.2 1957.72  4874.5 1958.01  4899.4 1950.94  4904.8 1951.72
  4924.3 1943.31  4929.7 1944.89  4935.9 1941.13  4946.6 1937.39  4954.6 1935.90
  4993.4 1934.58  4993.9 1934.08  5001.2 1934.58  5084.3 1943.65  5112.1 1951.62
  5158.1 1966.44  5200.3 1976.39  5242.4 1988.44  5284.6 1997.23  5316.2 2001.26
#Mann=5,-1,0
  4572.8     0.1       0  4856.3    0.07       0  4993.4    0.05       0
  5001.2    0.07       0  5112.1     0.1       0
Bank Sta=4993.4,5001.2
Exp/Cntr=0.3,0.1

Type RM Length L Ch R = 1,4211,468,468,468
BEGIN DESCRIPTION:
Indian Creek 02 9.0
END DESCRIPTION:
XS GIS Cut Line= 3
      1835275.00     13911375.00      1835275.00     13911225.00
      1835049.04     13910915.88
#Sta/Elev= 30
  4850.0 1950.15  4870.0 1948.97  4910.0 1943.79  4940.0 1934.78  4980.0 1932.43
  4986.0 1930.97  4986.5 1930.47  4993.9 1930.97  5003.1 1931.48  5007.3 1933.62
  5022.0 1934.35  5049.5 1933.16  5078.4 1934.55  5086.7 1940.34  5093.0 1947.46
  5099.2 1949.66  5107.7 1967.04  5120.8 1971.30  5149.4 1979.57  5157.9 1981.07
  5164.1 1983.57  5185.8 1988.42  5235.3 1995.52  5249.8 1998.42  5279.2 2000.88
  5300.0 2004.75  5350.2 2008.93  5364.9 2010.98  5371.6 2013.27  5382.9 2015.26
#Mann=4,-1,0
  4850.0    0.07       0  4986.0    0.05       0  4993.9    0.07       0
  5120.8     0.1       0
Bank Sta=4986,4993.9
Exp/Cntr=0.3,0.1

Type RM Length L Ch R = 1,3743,464,464,464
BEGIN DESCRIPTION:
Indian Creek 02 8.0
END DESCRIPTION:
XS GIS Cut Line= 3
      1835374.98     13911775.03      1835625.00     13911375.00
      1835782.59     13910940.00
#Sta/Elev= 30
  4520.8 1986.80  4549.7 1982.87  4601.6 1971.64  4622.8 1969.86  4659.4 1960.33
  4686.5 1956.48  4717.2 1949.05  4759.6 1941.94  4866.5 1934.04  4933.6 1929.30
  4948.3 1925.25  4980.9 1923.11  4981.4 1922.61  4988.9 1923.11  5002.5 1924.69
  5007.9 1931.19  5013.8 1934.71  5033.2 1942.98  5038.5 1956.66  5045.7 1968.28
  5063.8 1980.93  5094.4 1991.01  5186.3 2001.54  5211.7 2006.35  5242.3 2008.45
  5279.7 2014.88  5390.1 2024.91  5415.5 2029.63  5451.4 2033.74  5455.2 2035.31
#Mann=4,-1,0
  4520.8    0.07       0  4866.5     0.1       0  4980.9    0.05       0
  4988.9     0.1       0
Bank Sta=4980.9,4988.9
Exp/Cntr=0.3,0.1

Type RM Length L Ch R = 1,3279,468,468,468
BEGIN DESCRIPTION:
Indian Creek 02 7.0
END DESCRIPTION:
XS GIS Cut Line= 3
      1835774.99     13911925.04      1835825.00     13911775.00
      1835875.00     13911425.01
#Sta/Elev= 30
  4831.0 1979.62  4841.6 1978.56  4862.7 1970.46  4873.2 1963.95  4883.7 1947.50
  4894.3 1940.87  4904.8 1936.45  4915.4 1930.55  4925.9 1927.21  4936.5 1925.64
  4947.0 1921.35  4953.5 1920.09  4954.0 1919.59  4961.5 1920.09  5019.5 1922.51
  5029.6 1920.22  5039.7 1921.66  5059.9 1926.49  5070.0 1926.83  5080.1 1930.24
  5090.2 1931.16  5100.3 1936.11  5110.4 1937.63  5140.7 1940.33  5160.9 1941.13
  5187.2 1943.94  5211.4 1946.62  5261.9 1954.67  5322.5 1968.77  5342.7 1970.14
#Mann=4,-1,0
  4831.0    0.07       0  4953.5    0.05       0  4961.5    0.07       0
  5187.2     0.1       0
Bank Sta=4953.5,4961.5
Exp/Cntr=0.3,0.1

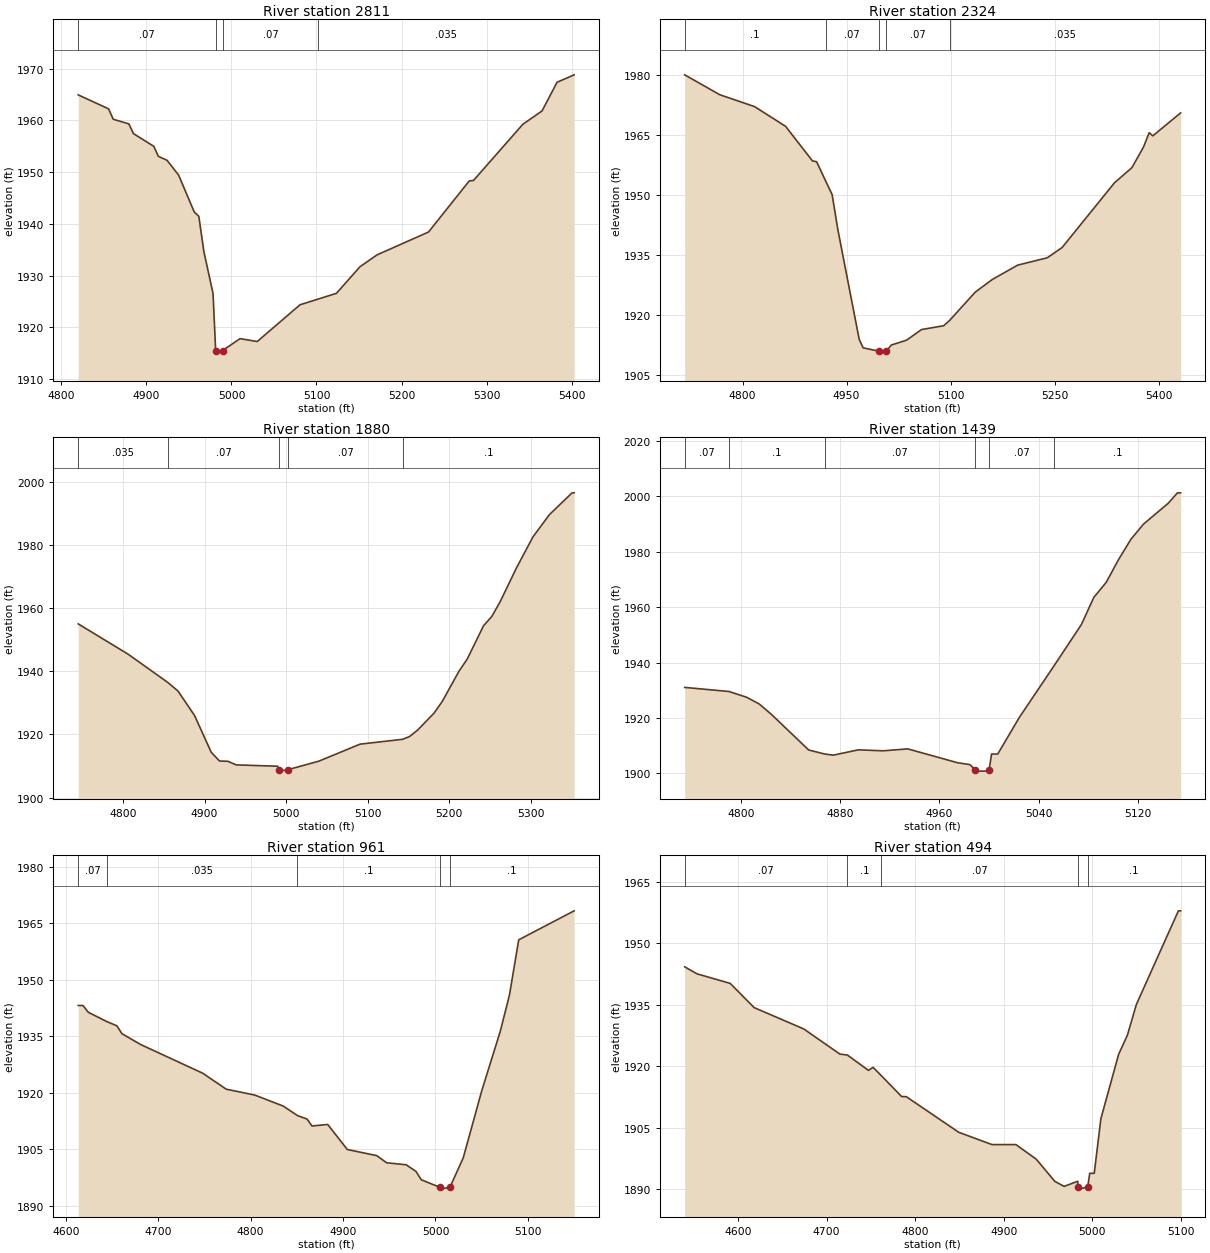
Type RM Length L Ch R = 1,2811,487,487,487
BEGIN DESCRIPTION:
Indian Creek 02 6.0
END DESCRIPTION:
XS GIS Cut Line= 3
      1836155.50     13912091.39      1836225.00     13911925.00
      1836175.00     13911525.03
#Sta/Elev= 30
  4819.7 1964.94  4855.5 1962.23  4860.9 1960.23  4879.3 1959.33  4884.7 1957.45
  4908.6 1955.00  4914.0 1953.06  4924.2 1952.30  4937.8 1949.44  4956.2 1942.32
  4961.6 1941.47  4967.5 1934.69  4978.3 1926.56  4981.4 1915.54  4981.9 1915.04
  4989.5 1915.54  5010.1 1917.84  5030.3 1917.28  5080.6 1924.38  5102.1 1925.49
  5123.5 1926.60  5151.2 1931.74  5171.3 1934.03  5231.8 1938.44  5279.7 1948.31
  5284.7 1948.40  5342.7 1959.25  5365.3 1961.83  5383.0 1967.37  5403.1 1968.81
#Mann=4,-1,0
  4819.7    0.07       0  4981.4    0.05       0  4989.5    0.07       0
  5102.1   0.035       0
Bank Sta=4981.4,4989.5
Exp/Cntr=0.3,0.1

Type RM Length L Ch R = 1,2324,444,444,444
BEGIN DESCRIPTION:
Indian Creek 02 5.0
END DESCRIPTION:
XS GIS Cut Line= 4
      1836803.94     13912082.71      1836720.37     13911915.73
      1836675.00     13911825.00      1836524.99     13911424.97
#Sta/Elev= 30
  4716.4 1980.14  4767.0 1975.17  4817.3 1972.19  4862.0 1967.26  4900.7 1958.63
  4906.7 1958.42  4919.9 1953.55  4929.1 1950.20  4937.5 1941.32  4968.2 1913.98
  4973.8 1911.90  4996.3 1911.07  4996.8 1910.57  5007.3 1911.07  5014.4 1912.59
  5036.6 1913.82  5058.0 1916.46  5090.0 1917.42  5098.9 1918.80  5135.4 1925.80
  5160.3 1929.00  5196.8 1932.57  5239.5 1934.41  5260.9 1936.98  5336.5 1953.17
  5361.5 1956.93  5378.4 1962.13  5386.4 1965.68  5391.7 1964.89  5431.8 1970.62
#Mann=5,-1,0
  4716.4     0.1       0  4919.9    0.07       0  4996.3    0.05       0
  5007.3    0.07       0  5098.9   0.035       0
Bank Sta=4996.3,5007.3
Exp/Cntr=0.3,0.1

Type RM Length L Ch R = 1,1880,441,441,441
BEGIN DESCRIPTION:
Indian Creek 02 4.0
END DESCRIPTION:
XS GIS Cut Line= 3
      1837075.00     13911824.99      1837025.00     13911575.00
      1837075.00     13911224.99
#Sta/Elev= 30
  4745.0 1955.00  4806.2 1945.40  4854.8 1936.47  4867.4 1933.74  4887.8 1925.95
  4908.2 1914.34  4918.4 1911.56  4928.6 1911.48  4938.8 1910.34  4989.7 1909.91
  4991.9 1908.86  4992.4 1908.36  5002.9 1908.86  5040.3 1911.52  5090.9 1916.91
  5142.9 1918.43  5151.5 1919.31  5161.6 1921.40  5181.8 1926.80  5191.9 1930.53
  5212.1 1939.97  5222.2 1943.81  5242.4 1954.43  5252.5 1957.36  5262.6 1961.96
  5282.8 1972.76  5303.0 1982.56  5323.2 1989.61  5351.0 1996.50  5353.5 1996.50
#Mann=5,-1,0
  4745.0   0.035       0  4854.8    0.07       0  4991.9    0.05       0
  5002.9    0.07       0  5142.9     0.1       0
Bank Sta=4991.9,5002.9
Exp/Cntr=0.3,0.1

Type RM Length L Ch R = 1,1439,478,478,478
BEGIN DESCRIPTION:
Indian Creek 02 3.0
END DESCRIPTION:
XS GIS Cut Line= 3
      1837375.00     13911575.03      1837375.00     13911325.00
      1837375.00     13911175.03
#Sta/Elev= 30
  4754.5 1931.03  4790.3 1929.54  4804.5 1927.46  4814.5 1925.08  4824.5 1921.27
  4854.5 1908.42  4867.3 1906.97  4874.5 1906.56  4894.5 1908.47  4914.5 1908.12
  4934.5 1908.81  4974.5 1903.82  4984.5 1903.14  4989.0 1901.28  4989.5 1900.78
  4999.6 1900.78  5000.1 1901.28  5002.0 1906.95  5007.0 1906.95  5024.5 1920.24
  5052.4 1938.82  5074.5 1953.76  5084.5 1963.55  5094.5 1968.98  5104.5 1977.25
  5114.5 1984.59  5124.5 1989.99  5144.5 1997.55  5152.0 2001.32  5154.5 2001.32
#Mann=6,-1,0
  4754.5    0.07       0  4790.3     0.1       0  4867.3    0.07       0
  4989.0    0.05       0  5000.1    0.07       0  5052.4     0.1       0
Bank Sta=4989,5000.1
Exp/Cntr=0.3,0.1

Type RM Length L Ch R = 1,961,467,467,467
BEGIN DESCRIPTION:
Indian Creek 02 2.0
END DESCRIPTION:
XS GIS Cut Line= 3
      1837696.01     13911689.56      1837825.00     13911325.00
      1837825.00     13911175.00
#Sta/Elev= 30
  4613.4 1943.17  4618.5 1943.17  4624.4 1941.34  4644.4 1938.89  4655.3 1937.76
  4660.7 1935.69  4680.9 1932.81  4748.1 1925.19  4773.6 1920.95  4804.6 1919.38
  4835.5 1916.44  4850.7 1913.94  4861.0 1913.03  4866.4 1911.18  4883.4 1911.59
  4904.6 1904.94  4936.5 1903.31  4947.1 1901.41  4968.3 1900.89  4978.9 1899.13
  4984.7 1896.90  5004.6 1894.92  5005.1 1894.42  5015.7 1894.92  5030.1 1902.74
  5050.1 1920.53  5070.1 1936.26  5080.1 1945.94  5090.1 1960.59  5150.1 1968.29
#Mann=5,-1,0
  4613.4    0.07       0  4644.4   0.035       0  4850.7     0.1       0
  5004.6    0.05       0  5015.7     0.1       0
Bank Sta=5004.6,5015.7
Exp/Cntr=0.3,0.1

Type RM Length L Ch R = 1,494,264,264,264
BEGIN DESCRIPTION:
Indian Creek 02 1.0
END DESCRIPTION:
XS GIS Cut Line= 3
      1838135.76     13911813.21      1838275.00     13911375.00
      1838275.00     13911275.00
#Sta/Elev= 30
  4539.8 1944.26  4553.7 1942.55  4591.2 1940.22  4618.2 1934.31  4674.3 1929.09
  4715.0 1922.96  4723.5 1922.73  4747.2 1918.99  4752.5 1919.72  4761.7 1917.71
  4784.7 1912.60  4790.0 1912.56  4849.2 1903.87  4886.7 1900.87  4913.7 1900.87
  4936.6 1897.32  4957.6 1891.90  4968.1 1890.67  4983.5 1891.92  4983.6 1890.50
  4984.1 1890.00  4994.7 1890.50  4997.0 1893.86  5002.1 1893.86  5009.6 1907.19
  5029.6 1922.88  5039.6 1927.62  5049.6 1935.04  5097.1 1957.93  5099.6 1957.93
#Mann=5,-1,0
  4539.8    0.07       0  4723.5     0.1       0  4761.7    0.07       0
  4983.6    0.05       0  4994.7     0.1       0
Bank Sta=4983.6,4994.7
Exp/Cntr=0.3,0.1

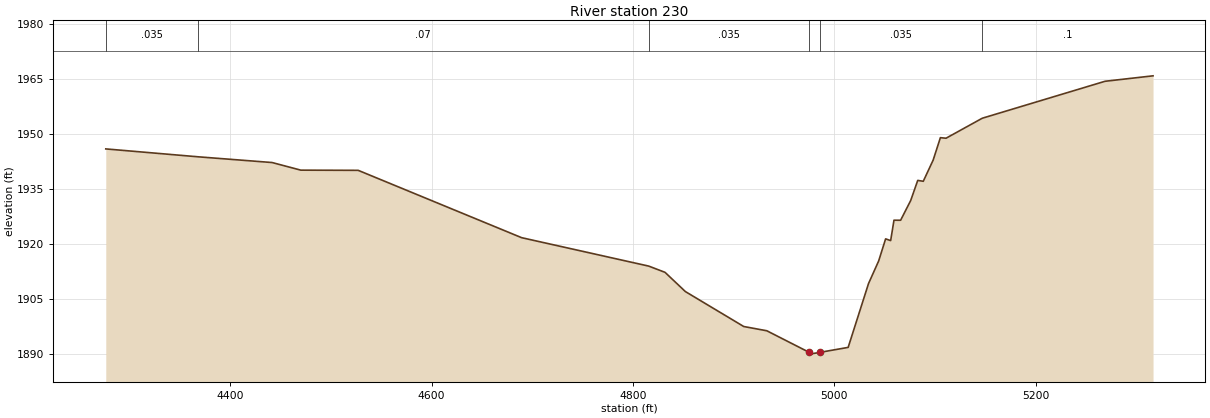
Type RM Length L Ch R = 1,230,0,0,0
BEGIN DESCRIPTION:
Indian Creek 02 0.0
END DESCRIPTION:
XS GIS Cut Line= 4
      1838094.41     13911967.61      1838494.97     13911619.46
      1838530.93     13911369.98      1838418.42     13911138.55
#Sta/Elev= 30
  4276.5 1945.89  4368.0 1943.74  4441.7 1942.17  4470.2 1940.09  4527.2 1940.04
  4689.5 1921.65  4815.7 1913.89  4831.9 1912.19  4852.1 1906.94  4910.1 1897.39
  4933.0 1896.23  4975.0 1890.35  4975.5 1889.85  4986.1 1890.35  5013.8 1891.69
  5034.0 1909.10  5044.1 1915.30  5051.0 1921.33  5056.0 1920.85  5059.3 1926.42
  5065.9 1926.41  5075.9 1931.79  5082.9 1937.29  5088.4 1937.05  5098.2 1942.83
  5105.4 1948.96  5111.0 1948.81  5147.0 1954.27  5268.9 1964.36  5316.6 1965.85
#Mann=6,-1,0
  4276.5   0.035       0  4368.0    0.07       0  4815.7   0.035       0
  4975.0   0.035       0  4986.1   0.035       0  5147.0     0.1       0
Bank Sta=4975,4986.1
Exp/Cntr=0.3,0.1

Chan Stop Cuts=-1