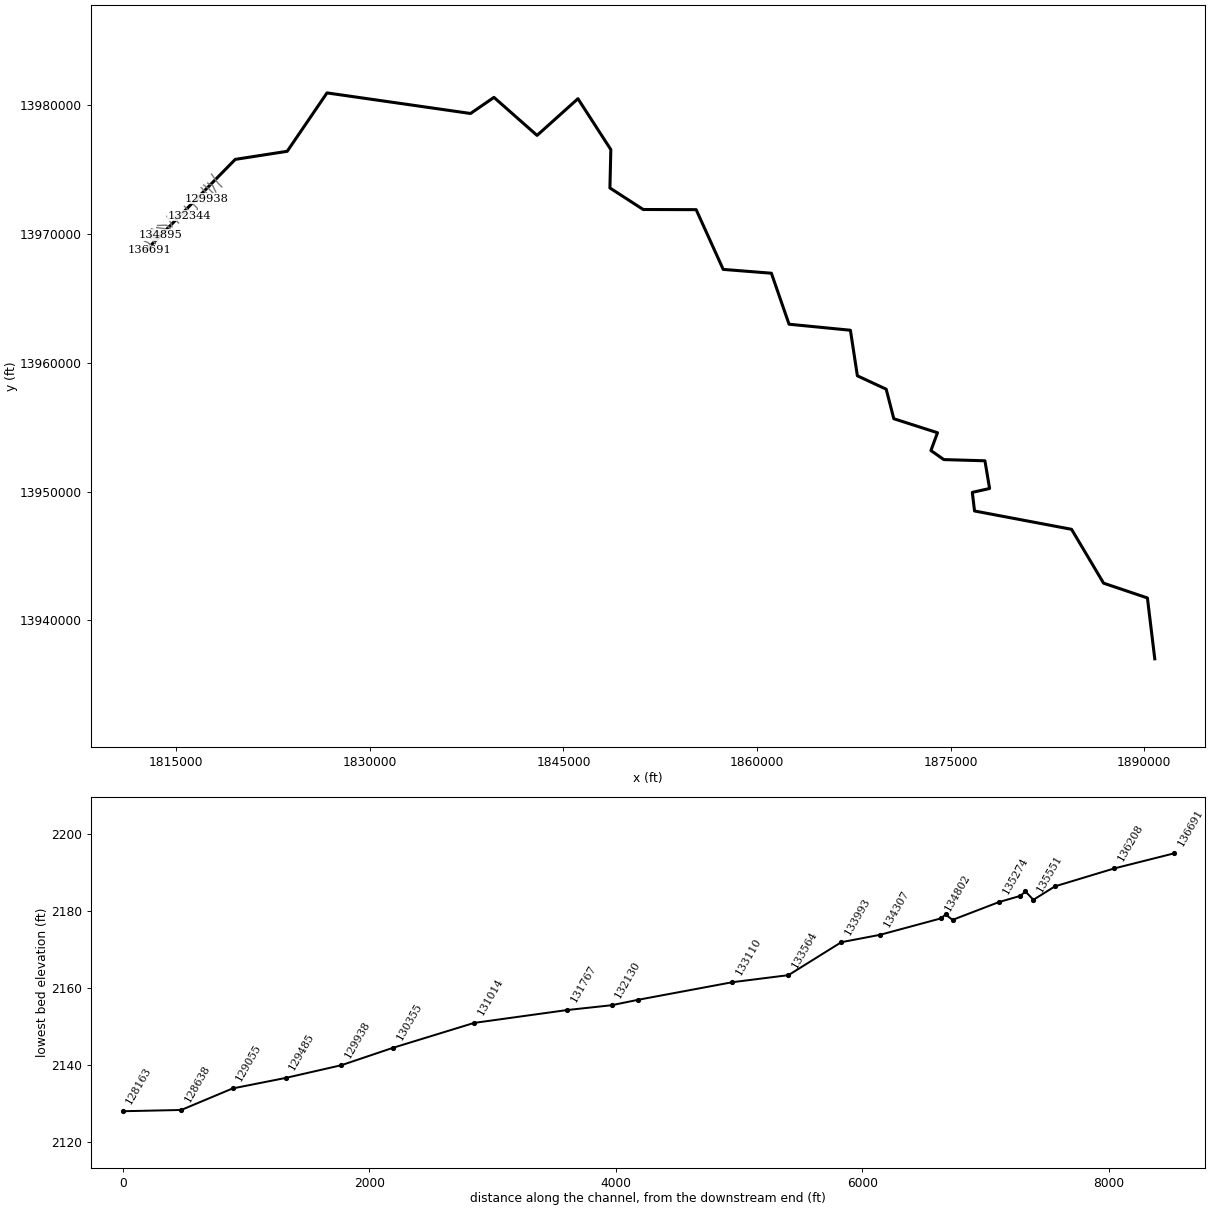
--- Johnson Creek.prj (project) ---

Proj Title=Johnson Creek Base Level Engineering
Current Plan=p01
Default Exp/Contr=0.3,0.1
English Units
Geom File=g01
Flow File=f01
Plan File=p01
Y Axis Title=Elevation
X Axis Title(PF)=Main Channel Distance
X Axis Title(XS)=Station
BEGIN DESCRIPTION:
Johnson Creek
END DESCRIPTION:
DSS Export Rating Curves= 0
DSS Export Rating Curve Sorted= 0
DSS Export Volume Flow Curves= 0
DXF OffsetX= 0
DXF OffsetY= 0
DXF ScaleX= 1
DXF ScaleY= 10

--- Johnson Creek.p01 (plan) ---

Plan Title=Multiple Run
Short Identifier=Multiple
Geom File=g01
Flow File=f01
Subcritical Flow
K Sum by GR= 0
Std Step Tol= 0.01
Critical Tol= 0.01
Num of Std Step Trials= 20
Max Error Tol= 0.3
Flow Tol Ratio= 0.001
Split Flow NTrial= 30
Split Flow Tol= 0.02
Split Flow Ratio= 0.02
Log Output Level= 0
Friction Slope Method= 1
Unsteady Friction Slope Method= 2
Unsteady Bridges Friction Slope Method= 1
Parabolic Critical Depth
Global Vel Dist=  1 , 1 , 1
Global Log Level= 0
CheckData=True
Encroach Param= -1, 0, 0, 0
BEGIN DESCRIPTION:
Multiple Run
END DESCRIPTION:

--- Johnson Creek.f01 (steady flow) ---

Flow Title=Multiple
Number of Profiles=7
Profile Names=10-year,25-year,50-year,1pct_min,100-year,1pct_plu,500-year
River Rch & RM= Johnson Creek,Reach-1,136691
     696    1148    1563    1029    2053    4096    3500
River Rch & RM= Johnson Creek,Reach-1,133564
    1765    3058    4302    2914    5815   11602   10513
River Rch & RM= Johnson Creek,Reach-1,130355
    2425    4271    6074    4156    8293   16546   15301
River Rch & RM= Johnson Creek,Reach-1,128163
    3099    5517    7903    5442   10859   21666   20298
River Rch & RM= Johnson Creek,Reach-1,125549
    3328    5937    8516    5871   11715   23374   21947
River Rch & RM= Johnson Creek,Reach-1,122276
    4244    7646   11040    7656   15277   30481   28960
River Rch & RM= Johnson Creek,Reach-1,119239
    4820    8720   12628    8780   17519   34954   33380
River Rch & RM= Johnson Creek,Reach-1,116311
    4960    8983   13016    9055   18066   36047   34460
River Rch & RM= Johnson Creek,Reach-1,115611
    5129    9294   13470    9372   18700   37312   35680
River Rch & RM= Johnson Creek,Reach-1,113041
    6602   12070   17605   12318   24578   49040   47423
River Rch & RM= Johnson Creek,Reach-1,107523
    6634   12122   17674   12361   24663   49210   47544
River Rch & RM= Johnson Creek,Reach-1,105301
    7318   13406   19577   13712   27359   54588   52885
River Rch & RM= Johnson Creek,Reach-1,102517
    7451   13648   19928   13955   27843   55554   53798
River Rch & RM= Johnson Creek,Reach-1,99659
    9580   17690   25977   18284   36482   72792   71209
River Rch & RM= Johnson Creek,Reach-1,96362
    9719   17950   26363   18558   37028   73880   72285
River Rch & RM= Johnson Creek,Reach-1,94693
    9824   18147   26656   18766   37444   74711   73116
River Rch & RM= Johnson Creek,Reach-1,90819
   10883   20173   29705   20961   41822   83445   82029
River Rch & RM= Johnson Creek,Reach-1,88594
   10892   20182   29708   20956   41812   83426   81953
River Rch & RM= Johnson Creek,Reach-1,84041
   14044   26182   38708   27410   54690  109122  107998
River Rch & RM= Johnson Creek,Reach-1,80231
   14061   26200   38723   27411   54693  109126  107928
River Rch & RM= Johnson Creek,Reach-1,77649
   16186   30252   44808   31781   63411  126523  125599
River Rch & RM= Johnson Creek,Reach-1,74314
   17111   31888   47150   33383   66608  132899  131392
River Rch & RM= Johnson Creek,Reach-1,68078
   17729   33043   48862   34596   69028  137728  136162
River Rch & RM= Johnson Creek,Reach-1,63326
   19335   36111   53481   37919   75659  150960  149648
River Rch & RM= Johnson Creek,Reach-1,61131
   19316   36048   53360   37813   75447  150536  149064
River Rch & RM= Johnson Creek,Reach-1,58481
   19302   36016   53305   37768   75358  150359  148843
River Rch & RM= Johnson Creek,Reach-1,57741
   19681   36697   54288   38445   76707  153051  151342
River Rch & RM= Johnson Creek,Reach-1,51430
   19706   36719   54297   38433   76683  153003  151148
River Rch & RM= Johnson Creek,Reach-1,48584
   21522   40169   59470   42141   84082  167765  166072
River Rch & RM= Johnson Creek,Reach-1,46250
   21846   40777   60376   42785   85367  170329  168626
River Rch & RM= Johnson Creek,Reach-1,44396
   21745   40552   60005   42495   84788  169175  167264
River Rch & RM= Johnson Creek,Reach-1,40689
   22061   41143   60881   43115   86025  171642  169697
River Rch & RM= Johnson Creek,Reach-1,38183
   22078   41140   60842   43061   85918  171430  169279
River Rch & RM= Johnson Creek,Reach-1,30779
   23761   44304   65556   46417   92614  184789  182603
River Rch & RM= Johnson Creek,Reach-1,25134
   23871   44479   65784   46555   92889  185339  182957
River Rch & RM= Johnson Creek,Reach-1,19830
   23939   44596   65947   46663   93105  185769  183323
River Rch & RM= Johnson Creek,Reach-1,17956
   23898   44490   65760   46508   92796  185153  182536
River Rch & RM= Johnson Creek,Reach-1,13171
   24924   46405   68601   48522   96813  193168  190452
River Rch & RM= Johnson Creek,Reach-1,5694
   24939   46418   68602   48509   96788  193118  190299
River Rch & RM= Johnson Creek,Reach-1,3811
   25002   46530   68765   48621   97011  193563  190711
River Rch & RM= Johnson Creek,Reach-1,2427
   24975   46458   68635   48513   96796  193134  190160
Boundary for River Rch & Prof#=Johnson Creek,Reach-1,1
Up Type=0
Dn Type=3
Dn Slope=0.005
Boundary for River Rch & Prof#=Johnson Creek,Reach-1,2
Up Type=0
Dn Type=3
Dn Slope=0.005
Boundary for River Rch & Prof#=Johnson Creek,Reach-1,3
Up Type=0
Dn Type=3
Dn Slope=0.005
Boundary for River Rch & Prof#=Johnson Creek,Reach-1,4
Up Type=0
Dn Type=3
Dn Slope=0.005
Boundary for River Rch & Prof#=Johnson Creek,Reach-1,5
Up Type=0
Dn Type=3
Dn Slope=0.005
Boundary for River Rch & Prof#=Johnson Creek,Reach-1,6
Up Type=0
Dn Type=3
Dn Slope=0.005
Boundary for River Rch & Prof#=Johnson Creek,Reach-1,7
Up Type=0
Dn Type=3
Dn Slope=0.005

--- Johnson Creek.g01 (geometry) ---

Geom Title=Existing Conditions
Program Version=4.10

River Reach=Johnson Creek   ,Reach-1
Reach XY= 30
      1812669.36     13968729.72      1819565.21      13975764.5
      1823592.53     13976391.64      1826676.56     13980921.26
      1837799.92      13979324.8       1839614.5     13980573.78
      1842954.87     13977624.61      1846123.42     13980471.17
      1848671.48     13976523.54      1848601.03     13973547.81
      1851180.86     13971877.06       1855284.8     13971864.52
      1857380.58     13967230.58      1861114.52      13966934.8
      1862483.34     13962977.98       1867238.3     13962511.66
      1867778.53     13958976.46      1870011.38     13957938.22
      1870601.47     13955647.86      1873988.24     13954561.38
      1873477.24     13953180.93       1874476.5     13952478.62
      1877663.89     13952385.32      1878023.78      13950235.5
      1876686.09     13949935.08      1876857.86     13948491.46
      1884377.43     13947069.48       1886858.2     13942891.41
      1890255.21     13941745.09        1890825.       13937025.

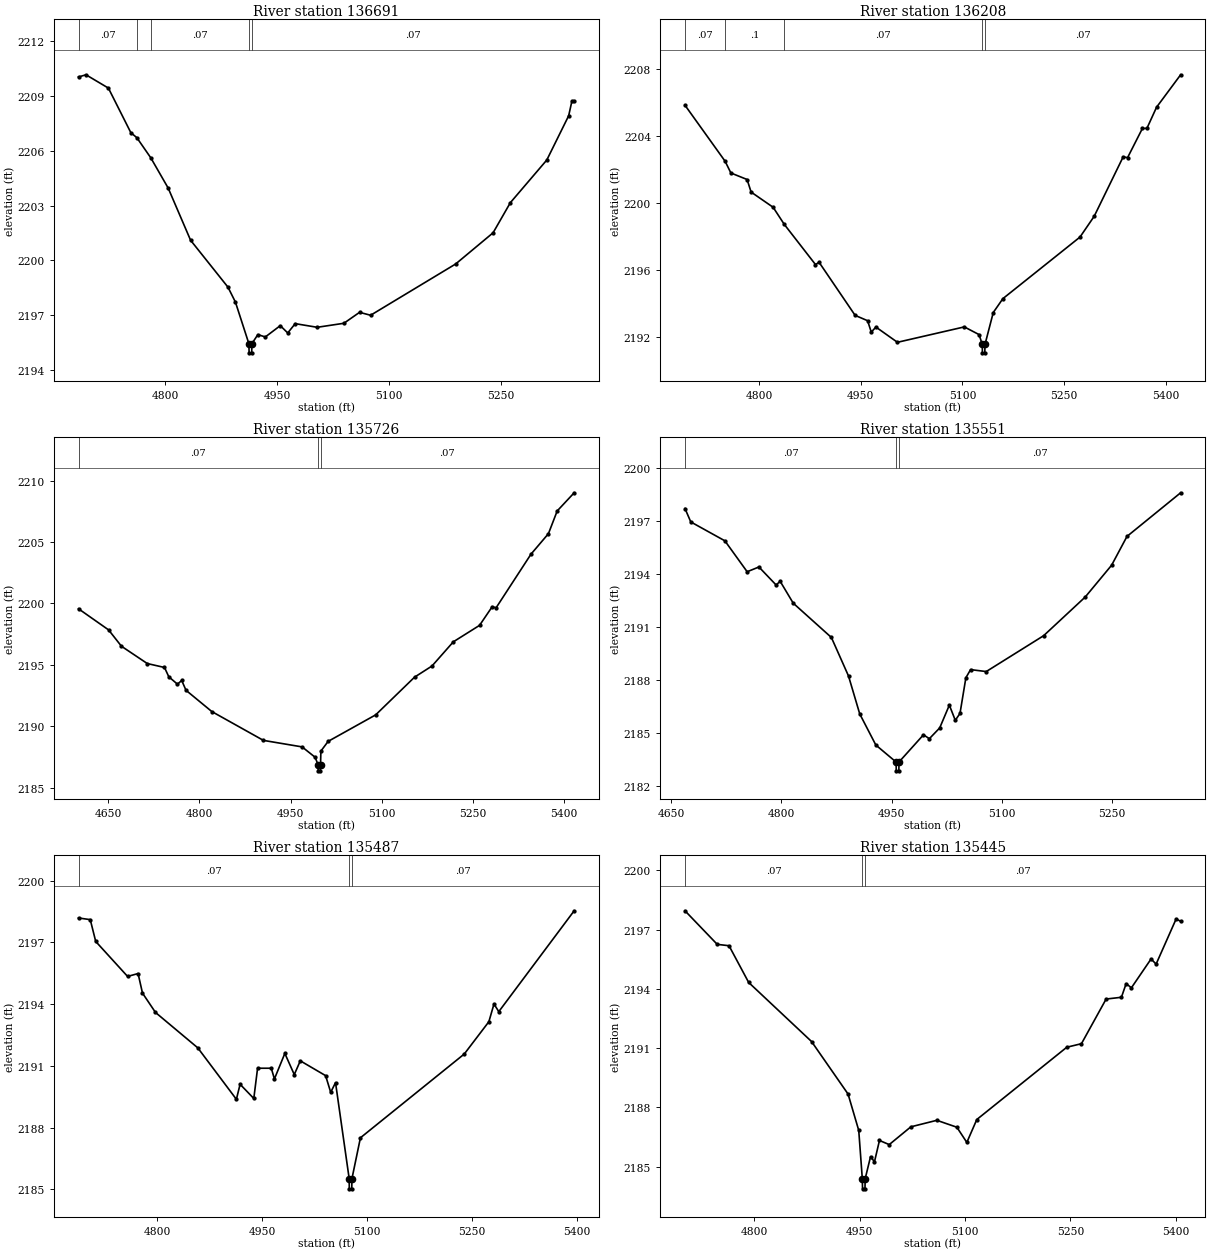
Type RM Length L Ch R = 1 ,136691  ,483,483,483
BEGIN DESCRIPTION:
Johnson Creek 204.0
END DESCRIPTION:
XS GIS Cut Line= 3
      1812324.98       13968925.      1812638.07     13968925.87
      1812924.96     13968725.03
#Sta/Elev= 30
  4684.3 2210.05  4694.3 2210.17  4724.3 2209.44  4754.3    2207  4762.4 2206.72
    4781 2205.62  4804.3 2203.96  4834.3  2201.1  4884.3 2198.53  4894.3 2197.71
  4912.3 2195.43  4912.6 2194.93  4916.1 2194.93  4916.3 2195.43  4924.3 2195.93
  4934.3  2195.8  4954.3 2196.42  4964.3 2196.02  4974.3 2196.53  5003.7 2196.33
  5039.4 2196.55  5060.4 2197.15  5075.2 2196.99    5189  2199.8  5239.1 2201.51
  5262.2 2203.16    5311  2205.5  5340.2 2207.92  5344.6 2208.73  5347.6 2208.73
#Mann= 5 ,-1 , 0
  4684.3     .07       0  4762.4      .1       0    4781     .07       0
  4912.3     .05       0  4916.3     .07       0
Bank Sta=4912.3,4916.3
XS Rating Curve= 0 ,0
Exp/Cntr=0.3,0.1

Type RM Length L Ch R = 1 ,136208  ,482,482,482
BEGIN DESCRIPTION:
Johnson Creek 203.0
END DESCRIPTION:
XS GIS Cut Line= 3
      1812525.01       13969425.      1812807.57      13969307.4
      1813124.98     13969025.02
#Sta/Elev= 30
  4690.9 2205.83  4750.1 2202.48  4758.6 2201.78  4782.5 2201.39  4788.4 2200.64
  4820.9 2199.73  4837.3 2198.71  4883.3 2196.31  4888.7 2196.44  4941.8 2193.27
  4960.2 2192.95  4965.6 2192.27  4972.5 2192.57  5004.2 2191.66  5102.8 2192.58
  5124.6 2192.12  5129.3 2191.53  5129.5 2191.03    5133 2191.03  5133.3 2191.53
  5145.5 2193.44  5159.7 2194.27  5273.4 2197.95  5294.3 2199.19    5337 2202.74
  5343.6  2202.7  5365.4 2204.44  5372.1 2204.45  5386.3 2205.71  5421.8 2207.65
#Mann= 5 ,-1 , 0
  4690.9     .07       0  4750.1      .1       0  4837.3     .07       0
  5129.3     .05       0  5133.3     .07       0
Bank Sta=5129.3,5133.3
XS Rating Curve= 0 ,0
Exp/Cntr=0.3,0.1

Type RM Length L Ch R = 1 ,135726  ,175,175,175
BEGIN DESCRIPTION:
Johnson Creek 202.0
END DESCRIPTION:
XS GIS Cut Line= 3
        1812825.       13969825.      1813110.52     13969546.31
      1813374.97     13969225.03
#Sta/Elev= 30
  4601.3 2199.56  4650.8 2197.84  4671.9 2196.51  4714.4  2195.1  4742.7 2194.78
  4749.8 2194.02    4764 2193.42    4771 2193.72  4778.1 2192.92  4820.5 2191.19
  4905.4 2188.84    4969 2188.31  4990.3 2187.47  4995.3 2186.86  4995.5 2186.36
    4999 2186.36  4999.3 2186.86  4999.9 2187.97  5011.8 2188.76    5090 2190.92
  5153.9 2193.99  5182.6  2194.9  5217.7 2196.87  5260.8 2198.21  5281.6 2199.73
    5288 2199.64  5345.4 2204.01  5374.1 2205.68  5388.5 2207.53  5416.4 2209.01
#Mann= 3 ,-1 , 0
  4601.3     .07       0  4995.3     .05       0  4999.3     .07       0
Bank Sta=4995.3,4999.3
XS Rating Curve= 0 ,0
Exp/Cntr=0.3,0.1

Type RM Length L Ch R = 1 ,135551  ,64,64,64
BEGIN DESCRIPTION:
Mapping XS 1b2fc26c
END DESCRIPTION:
XS GIS Cut Line= 4
      1812887.74      13969840.9      1813137.99     13969729.51
      1813233.77     13969653.71      1813418.69     13969445.69
#Sta/Elev= 30
  4668.9 2197.71  4676.8 2196.95  4723.2 2195.88  4753.5 2194.13  4769.5  2194.4
  4792.9 2193.38  4798.4 2193.59  4816.2 2192.35  4868.1 2190.41  4891.4 2188.23
  4906.7 2186.08  4928.6 2184.32  4956.1 2183.36  4956.4 2182.86  4959.9 2182.86
  4960.1 2183.36  4993.4  2184.9  5001.4 2184.68  5015.5 2185.29  5028.6 2186.58
  5036.7 2185.72  5043.1 2186.11  5051.1 2188.13  5057.5 2188.59  5078.8 2188.48
  5156.9 2190.51  5213.5  2192.7  5249.4  2194.5  5270.3 2196.13  5343.3  2198.6
#Mann= 3 ,-1 , 0
  4668.9     .07       0  4956.1     .05       0  4960.1     .07       0
Bank Sta=4956.1,4960.1
XS Rating Curve= 0 ,0
Exp/Cntr=0.3,0.1

Type RM Length L Ch R = 1 ,135487  ,42,42,42
BEGIN DESCRIPTION:
Mapping XS bdf9d409
END DESCRIPTION:
XS GIS Cut Line= 4
      1812889.29     13969869.54       1813144.7     13969773.77
      1813198.59     13969748.91      1813455.84     13969473.62
#Sta/Elev= 30
  4687.2 2198.19    4704 2198.11  4711.8 2197.05  4757.4 2195.35  4772.4 2195.49
  4778.7 2194.54  4797.3  2193.6  4857.8 2191.88    4913 2189.38  4918.3 2190.11
  4937.9 2189.42  4943.3 2190.89  4962.9 2190.89  4967.4 2190.37  4982.3 2191.61
  4995.8 2190.58  5004.4 2191.25  5040.6 2190.53  5047.9 2189.72  5054.8 2190.19
  5074.3 2185.53  5074.5 2185.03    5078 2185.03  5078.3 2185.53  5090.4 2187.51
  5238.9 2191.58  5274.1 2193.15  5281.4 2194.01  5288.3 2193.64  5396.1 2198.54
#Mann= 3 ,-1 , 0
  4687.2     .07       0  5074.3     .05       0  5078.3     .07       0
Bank Sta=5074.3,5078.3
XS Rating Curve= 0 ,0
Exp/Cntr=0.3,0.1

Type RM Length L Ch R = 1 ,135445  ,171,171,171
BEGIN DESCRIPTION:
Mapping XS 008f027b
END DESCRIPTION:
XS GIS Cut Line= 3
      1812927.13     13969929.56      1813233.99     13969776.84
       1813506.6     13969537.25
#Sta/Elev= 30
  4701.2 2197.96  4747.1 2196.26  4763.9 2196.19  4791.9 2194.33  4881.4 2191.34
  4933.4 2188.68  4948.6 2186.84  4953.7 2184.38    4954 2183.88  4957.5 2183.88
  4957.7 2184.38  4965.4 2185.51    4971 2185.25  4978.1 2186.33    4992 2186.12
  5022.8 2187.02  5059.8 2187.35  5088.3    2187  5102.5 2186.23  5116.7 2187.39
  5244.8 2191.05  5265.7 2191.23  5300.8 2193.49  5322.6 2193.58  5329.3 2194.27
  5336.8 2194.06  5364.8 2195.52    5372 2195.26  5400.4 2197.54  5406.9 2197.43
#Mann= 3 ,-1 , 0
  4701.2     .07       0  4953.7     .05       0  4957.7     .07       0
Bank Sta=4953.7,4957.7
XS Rating Curve= 0 ,0
Exp/Cntr=0.3,0.1

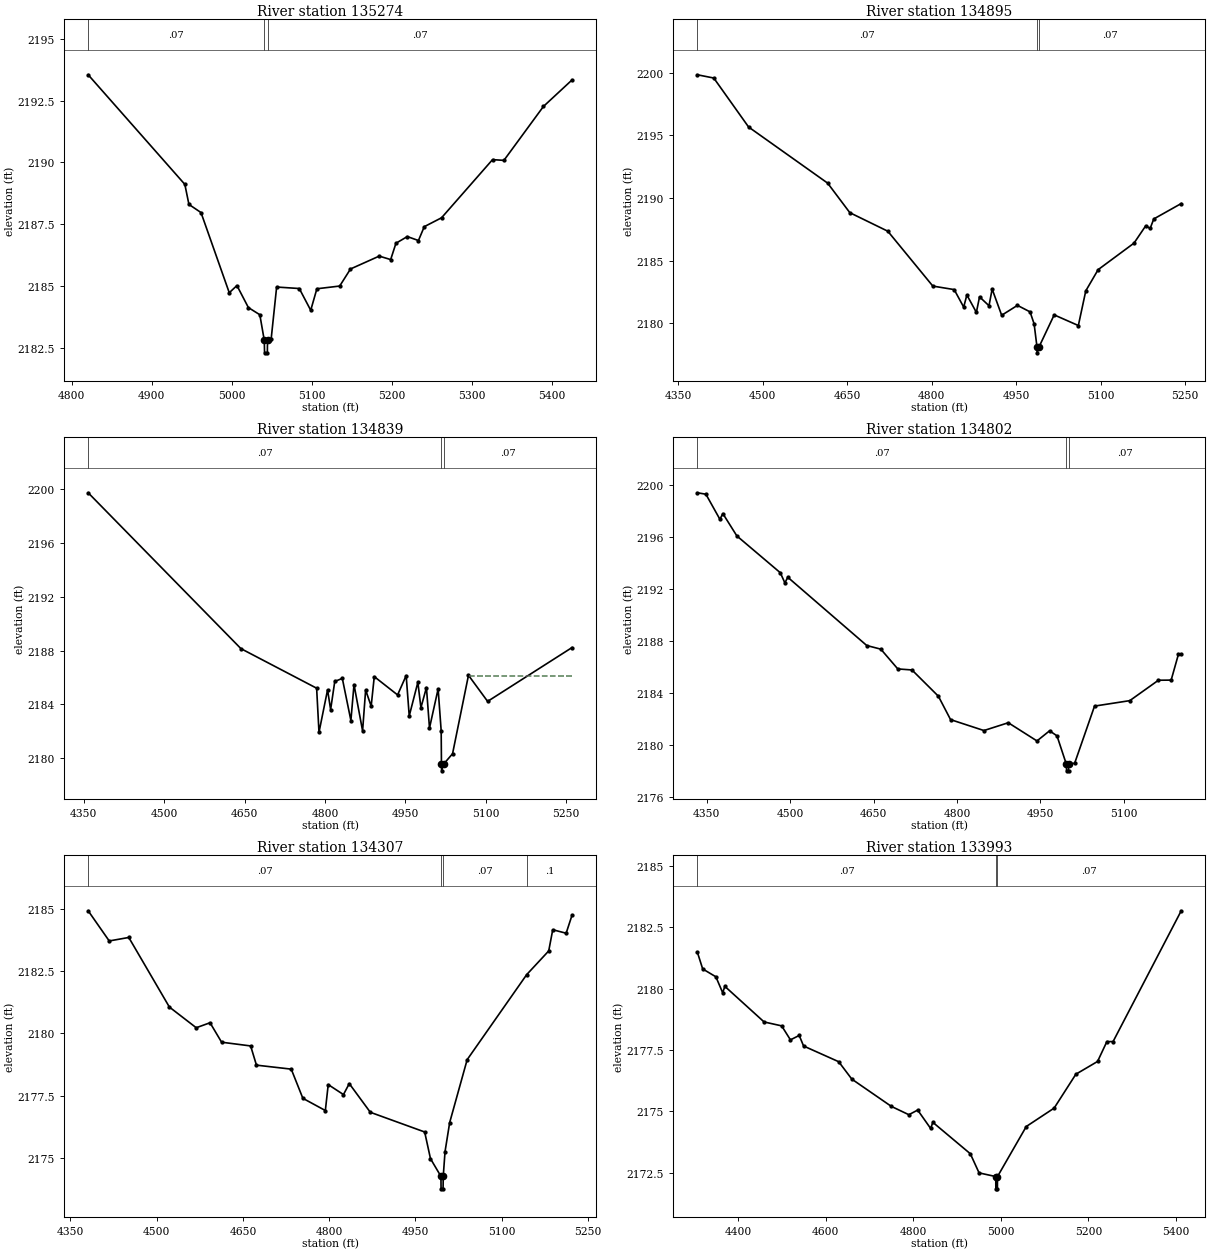
Type RM Length L Ch R = 1 ,135274  ,379,379,379
BEGIN DESCRIPTION:
Johnson Creek 201.0
END DESCRIPTION:
XS GIS Cut Line= 3
      1813075.02       13969975.      1813250.09       13969954.
      1813575.02     13969674.99
#Sta/Elev= 30
  4820.6 2193.54  4941.4 2189.11  4946.5  2188.3  4961.6 2187.97  4996.9 2184.73
  5006.5 2185.02  5020.8 2184.13  5035.1 2183.84  5040.7  2182.8    5041  2182.3
  5044.5  2182.3  5044.7  2182.8  5049.3 2182.87  5056.1 2184.96  5084.4  2184.9
  5098.7 2184.02  5106.4 2184.89  5134.9    2185  5148.4 2185.69  5184.3 2186.21
  5198.6 2186.07  5205.2 2186.73  5219.4    2187  5233.3 2186.84  5240.6  2187.4
  5262.2 2187.76  5325.9 2190.11  5340.1 2190.08  5389.5 2192.26  5425.2 2193.33
#Mann= 3 ,-1 , 0
  4820.6     .07       0  5040.7     .05       0  5044.7     .07       0
Bank Sta=5040.7,5044.7
XS Rating Curve= 0 ,0
Exp/Cntr=0.3,0.1

Type RM Length L Ch R = 1 ,134895  ,56,56,56
BEGIN DESCRIPTION:
Johnson Creek 200.2
END DESCRIPTION:
XS GIS Cut Line= 3
      1813060.13     13970330.98      1813587.83       13970071.
      1813794.22     13969896.09
#Sta/Elev= 30
  4384.2 2199.84  4413.3 2199.58  4475.1 2195.67  4615.4 2191.19  4654.8 2188.83
  4722.2 2187.35  4802.1 2182.97    4840 2182.69  4856.9 2181.29  4862.5 2182.26
  4879.4 2180.87    4885 2182.11  4901.8  2181.4  4907.4 2182.73  4924.3 2180.64
  4952.3 2181.43  4974.7 2180.91  4981.9 2179.95  4986.9 2178.14  4987.2 2177.64
  4990.9 2178.14  5017.5 2180.67  5060.4 2179.82  5073.6 2182.59  5095.5 2184.28
  5159.2  2186.4  5180.1 2187.79  5187.8 2187.57  5194.3 2188.33    5243 2189.56
#Mann= 3 ,-1 , 0
  4384.2     .07       0  4986.9     .05       0  4990.9     .07       0
Bank Sta=4986.9,4990.9
XS Rating Curve= 0 ,0
Exp/Cntr=0.3,0.1

Type RM Length L Ch R = 1 ,134839  ,37,37,37
BEGIN DESCRIPTION:
Johnson Creek 200.1
END DESCRIPTION:
XS GIS Cut Line= 4
      1813071.31     13970353.57      1813462.33     13970193.47
       1813671.9     13970077.51      1813868.68     13969939.49
#Sta/Elev= 30
  4358.4 2199.72  4643.3 2188.14  4784.5  2185.2  4788.9 2181.92  4804.9 2185.08
  4810.6 2183.61  4818.3  2185.7  4832.4 2185.93  4848.4  2182.8  4854.2 2185.47
  4870.2 2182.03  4875.9 2185.07  4886.2 2183.86    4892 2186.06  4935.5  2184.7
  4951.5 2186.14  4957.2 2183.14  4973.3 2185.64    4979 2183.75  4989.3 2185.25
    4995 2182.24  5011.1 2185.15  5016.8 2182.03  5017.3 2179.56  5017.6 2179.06
  5021.3 2179.56    5038 2180.33  5067.7 2186.16  5103.4 2184.22  5260.8 2188.22
#Mann= 3 ,-1 , 0
  4358.4     .07       0  5017.3     .05       0  5021.3     .07       0
#XS Ineff= 2 , 0
          4895.3 2185.88 5069.13         2186.13
Permanent Ineff=
       F       F
Bank Sta=5017.3,5021.3
XS Rating Curve= 0 ,0
Exp/Cntr=0.3,0.1

Type RM Length L Ch R = 1 ,134802  ,495,495,495
BEGIN DESCRIPTION:
Johnson Creek 200.0
END DESCRIPTION:
XS GIS Cut Line= 4
      1813074.96     13970375.02      1813434.32     13970243.61
      1813684.84      13970108.4      1813869.08     13970023.67
#Sta/Elev= 30
  4333.2 2199.43  4348.5 2199.32  4373.7 2197.39    4379 2197.83  4404.2 2196.11
  4482.3 2193.28  4490.5  2192.5  4495.8 2192.93  4637.8 2187.68  4663.1  2187.4
  4693.6 2185.88  4719.1  2185.8  4766.6 2183.78  4788.5 2181.98  4848.5 2181.14
  4892.3 2181.74  4943.9 2180.34  4966.6 2181.12  4979.9 2180.73  4996.8 2178.54
  4997.1 2178.04  5000.6 2178.04  5000.8 2178.54  5011.7 2178.63  5047.4 2183.02
  5110.8 2183.44  5162.3 2185.01  5185.2 2185.02  5198.3 2187.01  5203.3 2187.01
#Mann= 3 ,-1 , 0
  4333.2     .07       0  4996.8     .05       0  5000.8     .07       0
Bank Sta=4996.8,5000.8
XS Rating Curve= 0 ,0
Exp/Cntr=0.3,0.1

Type RM Length L Ch R = 1 ,134307  ,314,314,314
BEGIN DESCRIPTION:
Johnson Creek 199.0
END DESCRIPTION:
XS GIS Cut Line= 3
        1813475.       13970475.      1814090.05       13970393.
        1814125.     13970174.97
#Sta/Elev= 30
  4380.9 2184.91  4417.5  2183.7  4451.5 2183.84  4522.1 2181.05  4568.8 2180.22
  4592.8 2180.42  4612.9 2179.64  4663.4 2179.49  4673.5 2178.72    4734 2178.56
  4754.2 2177.39  4793.3  2176.9  4798.3 2177.94  4824.8 2177.54  4834.9 2177.98
  4871.5 2176.83    4966 2176.04  4976.1 2174.97  4994.3 2174.26  4994.5 2173.76
    4998 2173.76  4998.3 2174.26  5001.4 2175.25  5009.5 2176.42  5039.9 2178.94
  5143.4 2182.35  5181.7  2183.3  5188.7 2184.15    5212 2184.01  5222.2 2184.73
#Mann= 4 ,-1 , 0
  4380.9     .07       0  4994.3     .05       0  4998.3     .07       0
  5143.4      .1       0
#XS Ineff= 2 , 0
         4834.68 2177.96
Permanent Ineff=
       F       F
Bank Sta=4994.3,4998.3
XS Rating Curve= 0 ,0
Exp/Cntr=0.3,0.1

Type RM Length L Ch R = 1 ,133993  ,429,429,429
BEGIN DESCRIPTION:
Johnson Creek 198.0
END DESCRIPTION:
XS GIS Cut Line= 3
      1813542.89     13970637.57       1814235.1     13970666.52
      1814524.97     13970375.03
#Sta/Elev= 30
  4307.7 2181.48  4319.8  2180.8  4349.9 2180.48  4365.4 2179.83  4370.4 2180.09
  4459.9 2178.64    4500 2178.48    4520 2177.91    4540 2178.09    4550 2177.66
  4630.1 2177.02  4660.1 2176.31  4750.2  2175.2  4790.2 2174.86  4810.3 2175.05
  4839.9  2174.3  4844.9 2174.55  4930.4 2173.27  4950.4 2172.49  4988.4 2172.34
  4988.7 2171.84  4992.2 2171.84  4992.4 2172.34  5058.1 2174.38  5121.7 2175.13
  5171.2 2176.51  5220.7 2177.03    5242 2177.84  5256.1 2177.84  5411.6 2183.17
#Mann= 3 ,-1 , 0
  4307.7     .07       0  4988.4     .05       0  4992.4     .07       0
Bank Sta=4988.4,4992.4
XS Rating Curve= 0 ,0
Exp/Cntr=0.3,0.1

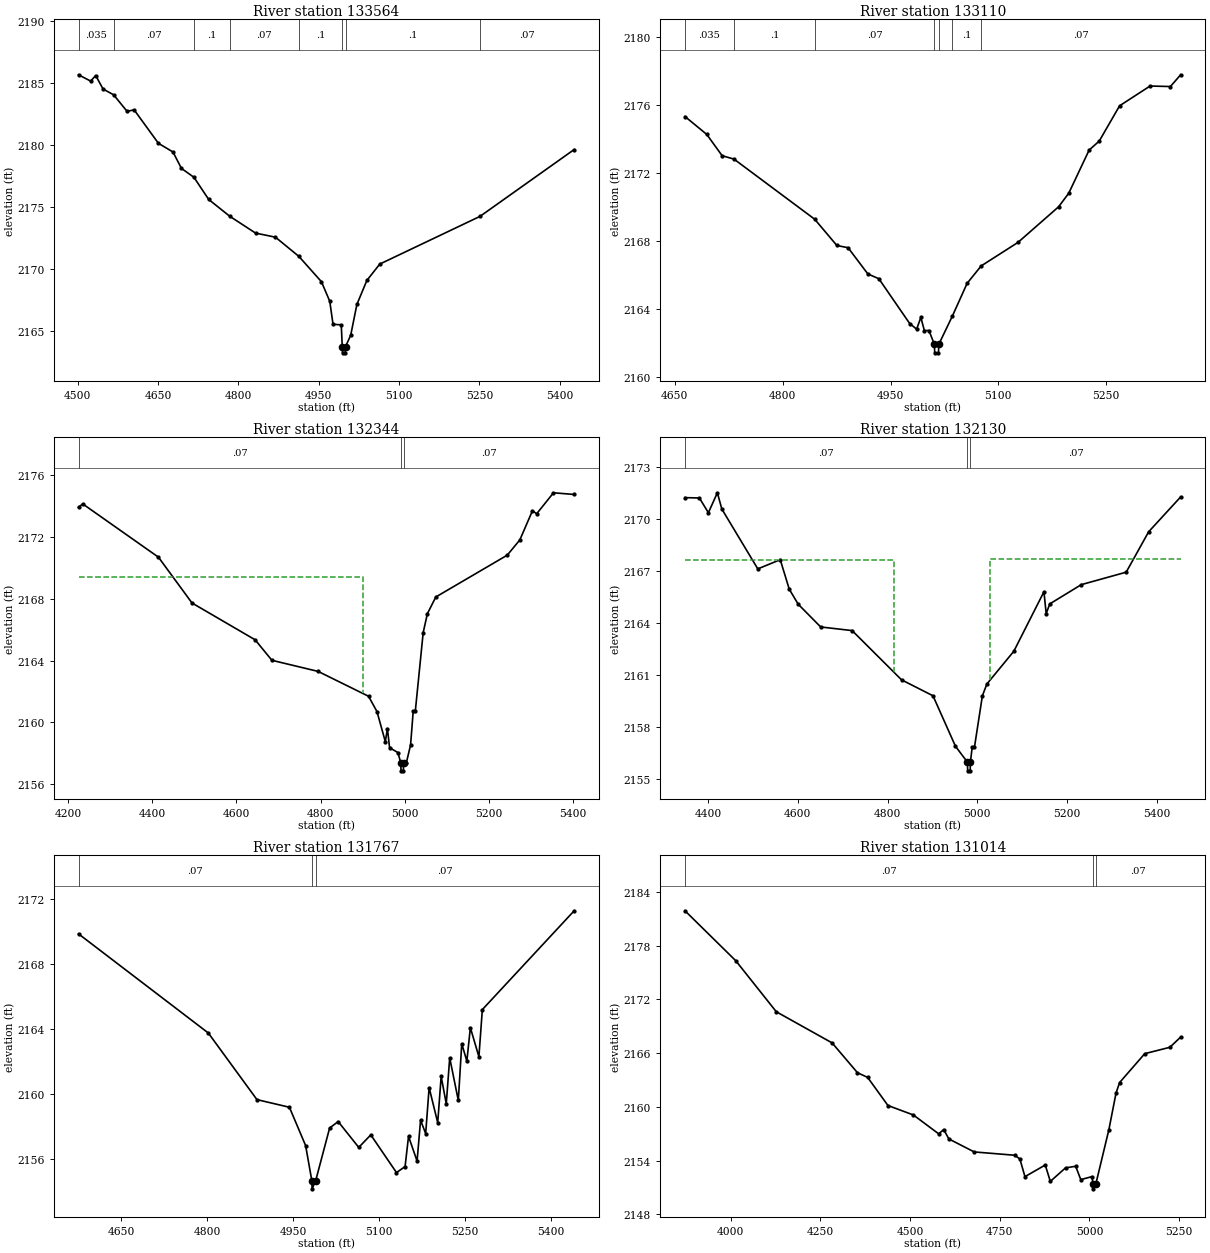
Type RM Length L Ch R = 1 ,133564  ,454,454,454
BEGIN DESCRIPTION:
Johnson Creek 197.0
END DESCRIPTION:
XS GIS Cut Line= 3
      1814271.82     13971354.53        1814525.       13970925.
        1814675.     13970524.99
#Sta/Elev= 30
  4501.3  2185.7    4524 2185.19  4533.4 2185.64  4547.2 2184.55    4567 2184.08
    4592 2182.75  4605.2 2182.87  4650.6 2180.17  4677.8 2179.47  4693.5 2178.15
  4716.9 2177.43  4744.5 2175.64    4784 2174.28    4832 2172.93  4869.1  2172.6
  4912.9 2171.05    4955 2169.01  4970.6 2167.43  4976.7 2165.57  4992.1 2165.53
  4993.9 2163.77  4994.4 2163.27  4999.5 2163.27    5000 2163.77  5009.7 2164.69
  5021.3 2167.18  5039.9 2169.11    5064 2170.43  5251.3 2174.28  5427.1 2179.67
#Mann= 8 ,-1 , 0
  4501.3    .035       0    4567     .07       0  4716.9      .1       0
    4784     .07       0  4912.9      .1       0  4993.9     .05       0
    5000      .1       0  5251.3     .07       0
Bank Sta=4993.9,5000
XS Rating Curve= 0 ,0
Exp/Cntr=0.3,0.1

Type RM Length L Ch R = 1 ,133110  ,766,766,766
BEGIN DESCRIPTION:
Johnson Creek 196.0
END DESCRIPTION:
XS GIS Cut Line= 3
      1814753.01     13971363.53        1814925.       13971075.
      1815175.03     13970824.97
#Sta/Elev= 30
  4664.1 2175.31  4694.4 2174.26  4715.8 2173.01  4732.3 2172.81  4844.6 2169.28
  4875.4 2167.74    4891 2167.61  4918.5 2166.07  4933.8 2165.79  4976.7 2163.16
  4986.4 2162.83  4992.2 2163.52  4997.1 2162.75  5003.5 2162.75    5011 2161.94
  5011.5 2161.44  5016.7 2161.44  5017.2 2161.94  5036.1  2163.6  5056.6 2165.52
  5076.1 2166.54  5127.3 2167.92  5183.8 2170.01    5198 2170.81  5226.3 2173.34
  5240.4 2173.87  5268.7 2175.94  5311.1  2177.1  5339.4 2177.07  5353.6 2177.76
#Mann= 7 ,-1 , 0
  4664.1    .035       0  4732.3      .1       0  4844.6     .07       0
    5011     .05       0  5017.2     .07       0  5036.1      .1       0
  5076.1     .07       0
Bank Sta=5011,5017.2
XS Rating Curve= 0 ,0
Exp/Cntr=0.3,0.1

Type RM Length L Ch R = 1 ,132344  ,214,214,214
BEGIN DESCRIPTION:
Johnson Creek 195.0
END DESCRIPTION:
XS GIS Cut Line= 3
      1814804.97     13971368.17      1815602.62     13971381.01
      1815984.17     13971380.84
#Sta/Elev= 30
  4224.2 2173.93  4234.2 2174.15  4414.3  2170.7  4494.3 2167.73  4644.3 2165.35
  4684.3 2164.02  4794.3  2163.3  4914.3 2161.69  4934.3  2160.7  4954.2 2158.75
  4959.2  2159.6  4964.3 2158.36  4984.3 2158.04    4991 2157.36  4991.5 2156.86
  4997.1 2156.86  4997.6 2157.36  5004.3 2157.39  5014.3 2158.54  5020.6 2160.74
  5025.6 2160.74  5044.3 2165.82  5054.3 2167.04  5074.3 2168.12  5244.3 2170.83
  5274.3 2171.82  5304.3 2173.71  5314.3 2173.51  5354.3 2174.87  5403.5 2174.76
#Mann= 3 ,-1 , 0
  4224.2     .07       0    4991     .05       0  4997.6     .07       0
#XS Ineff= 2 , 0
          4900.7 2169.42
Permanent Ineff=
       F       F
Bank Sta=4991,4997.6
XS Rating Curve= 0 ,0
Exp/Cntr=0.3,0.1

Type RM Length L Ch R = 1 ,132130  ,363,363,363
BEGIN DESCRIPTION:
Johnson Creek 194.0
END DESCRIPTION:
XS GIS Cut Line= 3
      1815072.87     13971538.65      1815714.52     13971537.67
      1816176.22     13971544.42
#Sta/Elev= 30
  4349.1 2171.21  4381.2 2171.19  4401.2 2170.34  4421.2 2171.49  4431.2 2170.55
  4511.2  2167.1  4561.2 2167.63  4581.2 2165.93  4601.2 2165.06  4651.2 2163.75
  4721.2 2163.54  4831.2  2160.7  4901.2 2159.78  4951.2 2156.87  4977.9 2155.95
  4978.4 2155.45    4984 2155.45  4984.5 2155.95  4988.5 2156.81  4993.5 2156.81
  5011.2 2159.78  5021.2 2160.46  5081.2 2162.35  5148.2 2165.78  5153.2 2164.52
  5161.2 2165.08  5231.3 2166.19  5331.3 2166.91  5381.3 2169.24  5452.5 2171.25
#Mann= 3 ,-1 , 0
  4349.1     .07       0  4977.9     .05       0  4984.5     .07       0
#XS Ineff= 2 , 0
         4815.38 2167.62 5027.97         2167.65
Permanent Ineff=
       F       F
Bank Sta=4977.9,4984.5
XS Rating Curve= 0 ,0
Exp/Cntr=0.3,0.1

Type RM Length L Ch R = 1 ,131767  ,753,753,753
BEGIN DESCRIPTION:
Johnson Creek 193.0
END DESCRIPTION:
XS GIS Cut Line= 3
      1815625.01     13972124.99        1815925.       13971825.
      1816288.74     13971577.52
#Sta/Elev= 30
    4576 2169.88  4802.3 2163.78  4887.1 2159.68  4943.7 2159.21    4972 2156.85
  4982.8 2154.69  4983.3 2154.19  4989.5 2154.69  5013.8 2157.93  5028.7 2158.33
  5064.6 2156.74  5085.6 2157.51  5130.4 2155.19  5145.4 2155.56  5151.4 2157.42
  5166.3  2155.9  5172.4 2158.41  5181.3 2157.59  5187.3 2160.42  5202.3 2158.26
  5208.3 2161.11  5217.2 2159.42  5223.2 2162.25  5238.2 2159.63  5244.2 2163.12
  5253.1 2162.05  5259.2 2164.11  5274.1 2162.32  5280.1 2165.22  5440.2  2171.3
#Mann= 3 ,-1 , 0
    4576     .07       0  4982.8     .05       0  4989.5     .07       0
Bank Sta=4982.8,4989.5
XS Rating Curve= 0 ,0
Exp/Cntr=0.3,0.1

Type RM Length L Ch R = 1 ,131014  ,659,659,659
BEGIN DESCRIPTION:
Johnson Creek 191.0
END DESCRIPTION:
XS GIS Cut Line= 3
      1815825.01     13972774.99        1816625.       13971975.
        1816625.     13971724.95
#Sta/Elev= 30
  3872.9 2181.89  4014.3 2176.32  4127.4 2170.62    4283 2167.14  4353.7 2163.81
    4382 2163.29  4438.6 2160.15  4509.3  2159.1    4580 2156.99  4594.1 2157.47
  4608.3 2156.42    4679 2154.97  4792.1  2154.6  4806.3 2154.18  4820.4 2152.21
    4877 2153.51  4891.1 2151.68  4933.5 2153.19  4961.8 2153.37    4976 2151.88
  5006.8 2152.21  5010.9 2151.35  5011.4 2150.85  5017.7 2151.35  5054.3 2157.45
  5074.3 2161.55  5084.3 2162.72  5154.3 2165.94  5224.3 2166.65  5254.3 2167.79
#Mann= 3 ,-1 , 0
  3872.9     .07       0  5010.9     .05       0  5017.7     .07       0
Bank Sta=5010.9,5017.7
XS Rating Curve= 0 ,0
Exp/Cntr=0.3,0.1

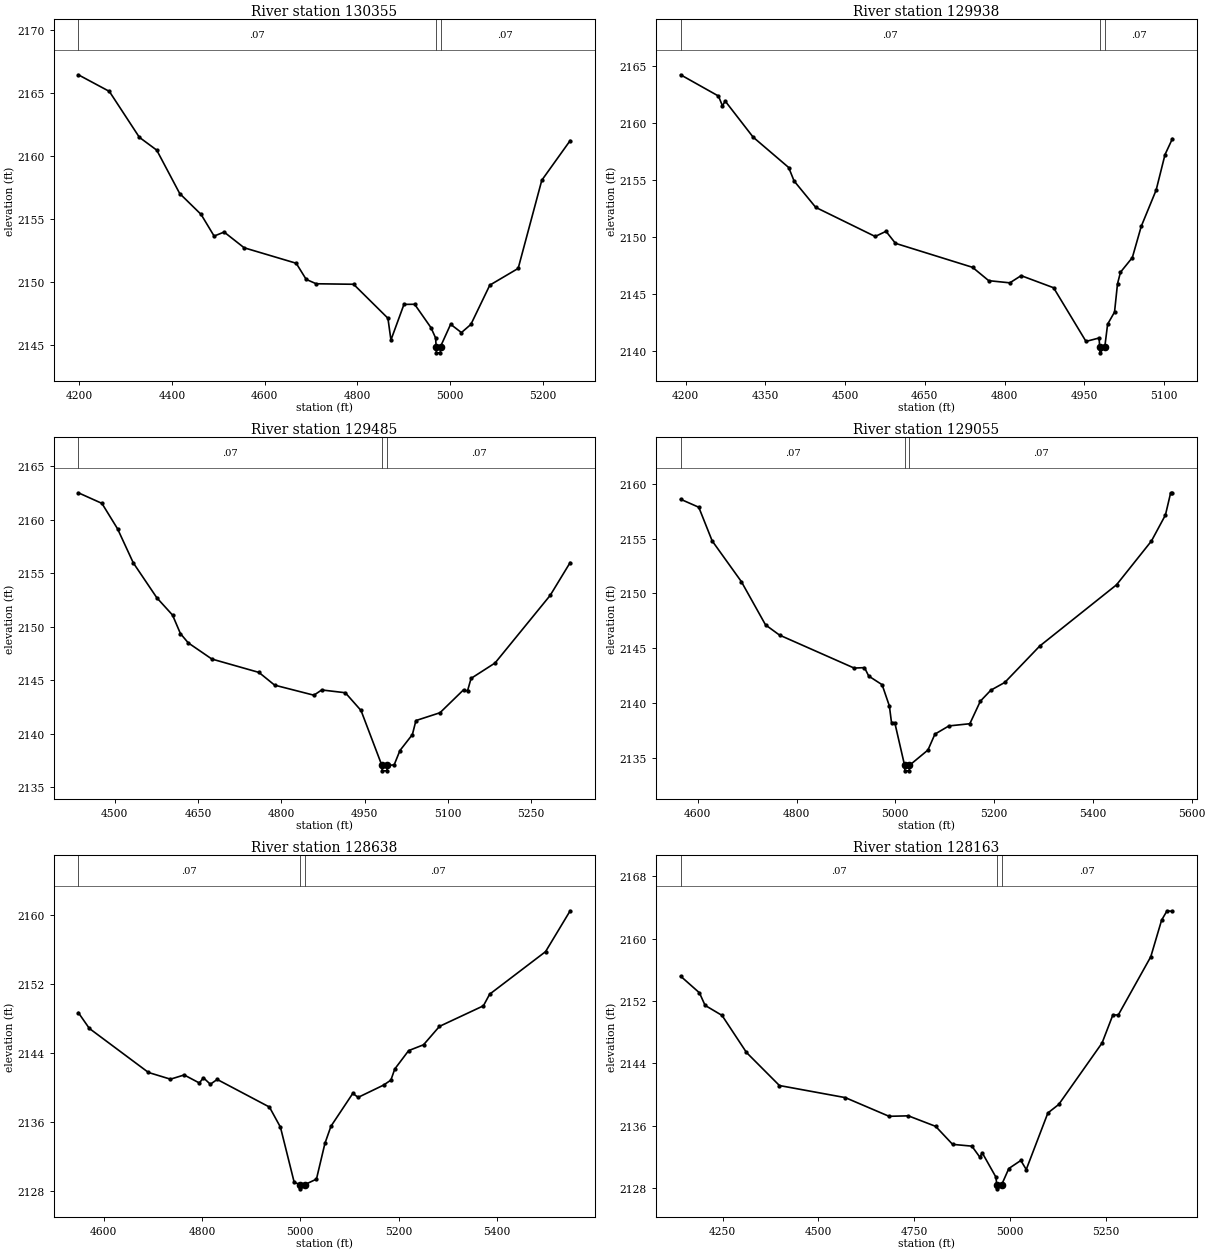
Type RM Length L Ch R = 1 ,130355  ,417,417,417
BEGIN DESCRIPTION:
Johnson Creek 190.0
END DESCRIPTION:
XS GIS Cut Line= 3
      1816375.01       13972825.        1817075.       13972425.
      1817325.03     13972374.99
#Sta/Elev= 30
  4198.1 2166.47    4265 2165.15  4329.8  2161.5  4367.3 2160.48  4416.9 2157.03
    4463 2155.37  4491.1 2153.65  4512.7 2153.97  4555.9 2152.72  4668.2 2151.49
  4689.7 2150.21  4711.3 2149.86    4792 2149.82  4866.1 2147.12  4872.6 2145.39
  4900.7 2148.22  4923.7 2148.23    4959 2146.37    4969 2145.55  4970.1 2144.87
  4970.6 2144.37  4979.1 2144.37  4979.6 2144.87  5001.4 2146.64  5024.7 2145.98
  5045.1 2146.63  5085.9 2149.75  5147.1 2151.08  5198.1 2158.09  5259.3 2161.24
#Mann= 3 ,-1 , 0
  4198.1     .07       0  4970.1     .05       0  4979.6     .07       0
Bank Sta=4970.1,4979.6
XS Rating Curve= 0 ,0
Exp/Cntr=0.3,0.1

Type RM Length L Ch R = 1 ,129938  ,453,453,453
BEGIN DESCRIPTION:
Johnson Creek 189.0
END DESCRIPTION:
XS GIS Cut Line= 3
      1816475.03     13972924.99        1817275.       13972775.
      1817374.99       13972725.
#Sta/Elev= 30
  4190.3 2164.21  4261.5 2162.35  4269.1 2161.49  4274.2 2161.91  4326.8 2158.75
  4393.7 2156.09  4403.9 2154.91  4444.6  2152.6  4556.5 2150.05  4576.9  2150.5
  4594.7 2149.45  4739.7 2147.35  4770.2 2146.18    4810 2145.99  4831.2 2146.62
  4892.3 2145.56  4953.3 2140.86  4977.9 2141.16  4979.1 2140.36  4979.6 2139.86
  4988.6 2140.36    4994 2142.37    5007 2143.43  5012.6 2145.91  5018.2 2146.92
  5040.5  2148.2  5057.3 2150.94  5085.3 2154.11    5102 2157.22    5116 2158.62
#Mann= 3 ,-1 , 0
  4190.3     .07       0  4979.1     .05       0  4988.6     .07       0
Bank Sta=4979.1,4988.6
XS Rating Curve= 0 ,0
Exp/Cntr=0.3,0.1

Type RM Length L Ch R = 1 ,129485  ,430,430,430
BEGIN DESCRIPTION:
Johnson Creek 188.0
END DESCRIPTION:
XS GIS Cut Line= 3
      1816924.97     13973575.03        1817325.       13973175.
      1817525.01     13972924.98
#Sta/Elev= 30
  4434.2 2162.53  4476.7 2161.54  4504.9 2159.16  4533.2 2155.98  4575.7 2152.71
  4603.9  2151.1  4618.1 2149.37  4632.2  2148.5  4674.7 2146.99  4759.5 2145.74
  4787.8 2144.55  4858.5 2143.61  4872.6  2144.1  4915.1 2143.84  4943.4 2142.18
    4981 2137.04  4981.5 2136.54  4990.1 2136.54  4990.6 2137.04  5003.1  2137.1
  5013.5 2138.44  5035.9 2139.93  5042.3 2141.24  5085.6 2141.97    5128 2144.11
  5135.2 2144.01  5141.6 2145.18  5184.8 2146.62  5284.1 2152.94  5320.1 2156.01
#Mann= 3 ,-1 , 0
  4434.2     .07       0    4981     .05       0  4990.6     .07       0
Bank Sta=4981,4990.6
XS Rating Curve= 0 ,0
Exp/Cntr=0.3,0.1

Type RM Length L Ch R = 1 ,129055  ,417,417,417
BEGIN DESCRIPTION:
Johnson Creek 187.0
END DESCRIPTION:
XS GIS Cut Line= 3
      1817125.03     13973774.98        1817475.       13973525.
      1817875.03     13973124.97
#Sta/Elev= 30
  4565.3  2158.6  4602.1 2157.87  4629.2  2154.8  4688.2 2151.09  4737.3 2147.13
  4765.6  2146.2  4916.7 2143.19  4937.6 2143.23  4946.2 2142.46  4973.3 2141.67
    4988 2139.73  4992.3 2138.21  4998.9 2138.21  5018.8 2134.31  5019.3 2133.81
  5028.1 2133.81  5028.6 2134.31  5066.1 2135.71  5080.2 2137.16  5108.5 2137.91
  5150.9 2138.11  5172.2 2140.17  5193.4 2141.17  5221.7 2141.88  5292.4  2145.2
  5447.9 2150.79  5518.6 2154.79  5546.9 2157.16  5557.5 2159.19  5561.1 2159.19
#Mann= 3 ,-1 , 0
  4565.3     .07       0  5018.8     .05       0  5028.6     .07       0
Bank Sta=5018.8,5028.6
XS Rating Curve= 0 ,0
Exp/Cntr=0.3,0.1

Type RM Length L Ch R = 1 ,128638  ,475,475,475
BEGIN DESCRIPTION:
Johnson Creek 186.0
END DESCRIPTION:
XS GIS Cut Line= 3
      1817424.98     13973925.01        1817825.       13973725.
      1818061.77     13973225.63
#Sta/Elev= 30
  4548.6  2148.7    4571 2146.86  4691.2 2141.74  4735.9 2140.96  4763.8 2141.45
  4794.6 2140.52    4803 2141.12    4817 2140.37  4830.9 2140.93  4937.1 2137.72
  4959.5 2135.38  4987.5 2128.96  4999.5 2128.71    5000 2128.21  5009.4 2128.71
  5032.7 2129.34  5049.9 2133.49  5062.2 2135.49  5106.5  2139.3  5117.6 2138.85
  5169.1 2140.27    5184 2140.85  5191.9 2142.14  5220.1 2144.28  5250.4 2144.96
  5282.8  2147.1  5372.1 2149.49  5384.8 2150.84  5498.5 2155.79  5548.5 2160.54
#Mann= 3 ,-1 , 0
  4548.6     .07       0  4999.5     .05       0  5009.4     .07       0
Bank Sta=4999.5,5009.4
XS Rating Curve= 0 ,0
Exp/Cntr=0.3,0.1

Type RM Length L Ch R = 1 ,128163  ,417,417,417
BEGIN DESCRIPTION:
Johnson Creek 185.0
END DESCRIPTION:
XS GIS Cut Line= 3
      1817724.99     13974625.01        1818225.       13973925.
      1818524.99     13973625.01
#Sta/Elev= 30
    4140 2155.18  4189.2 2153.04  4203.9 2151.43  4248.2 2150.14  4312.1 2145.38
  4398.1 2141.14  4570.1 2139.59  4684.4 2137.19  4734.8 2137.25  4806.1  2135.9
  4850.3 2133.59  4900.7 2133.36  4921.6 2131.94  4927.7 2132.51  4963.4 2129.39
  4965.8 2128.38  4966.3 2127.88  4978.2 2128.38  4997.2 2130.49  5028.5 2131.52
  5042.7 2130.36  5099.2 2137.62  5127.5 2138.71  5240.7  2146.6  5268.9  2150.2
  5283.1  2150.2  5367.9 2157.67  5396.2 2162.37  5410.4 2163.57  5424.5 2163.49
#Mann= 3 ,-1 , 0
    4140     .07       0  4965.8     .05       0  4978.2     .07       0
Bank Sta=4965.8,4978.2
XS Rating Curve= 0 ,0
Exp/Cntr=0.3,0.1