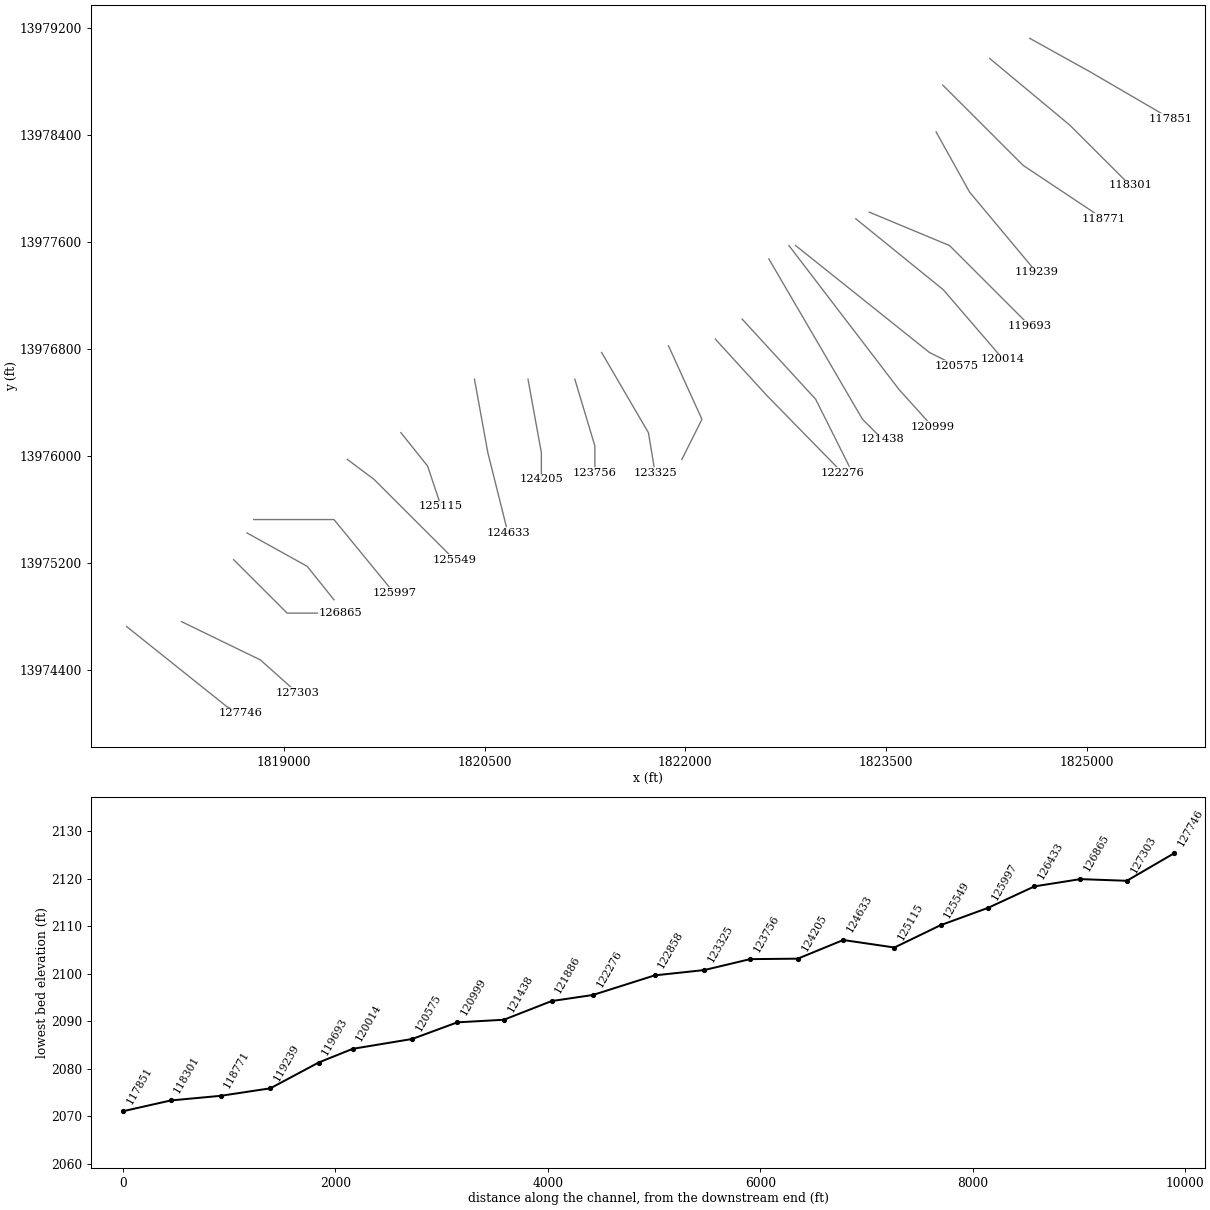
HEC-RAS study Johnson Creek.prj: Johnson Creek Base Level Engineering

--- Johnson Creek.g01 (geometry) --- (continued)

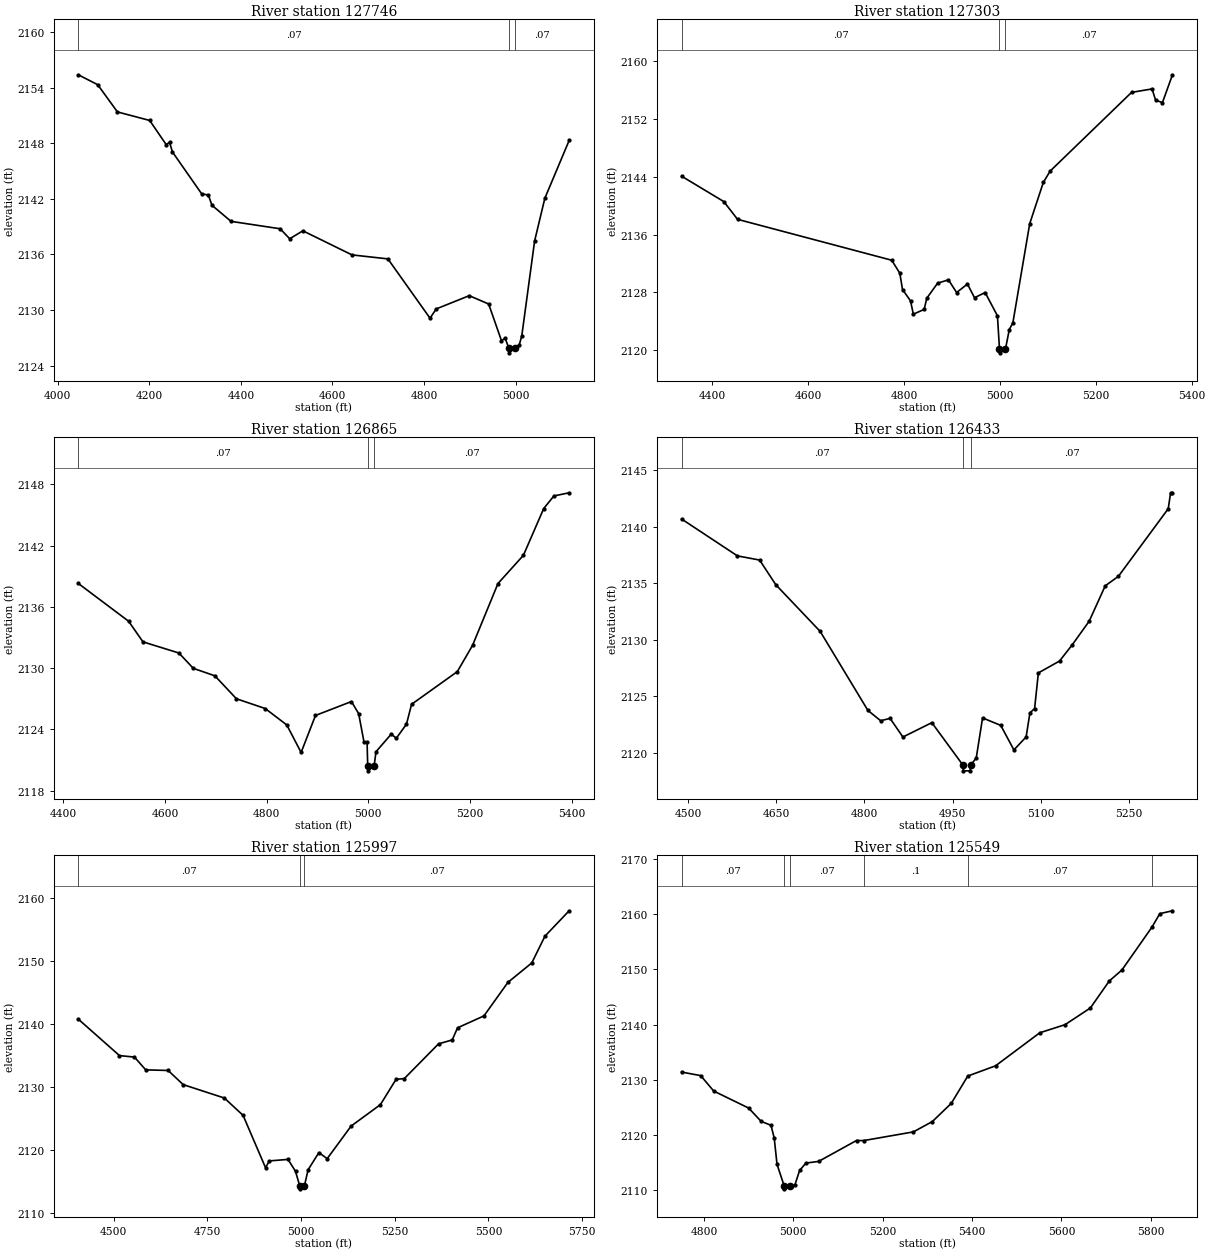
Type RM Length L Ch R = 1 ,127746  ,443,443,443
BEGIN DESCRIPTION:
Johnson Creek 184.0
END DESCRIPTION:
XS GIS Cut Line= 3
      1817825.03     13974724.97        1818575.       13974125.
      1818674.97     13974075.01
#Sta/Elev= 30
  4044.7 2155.38  4087.1 2154.31  4130.3 2151.37  4200.7 2150.45  4236.8 2147.84
    4244  2148.1  4250.4 2147.05  4314.4 2142.52  4328.8 2142.41  4336.8 2141.29
  4378.4 2139.56  4485.7 2138.76  4506.5 2137.68  4535.3 2138.54  4642.6 2135.94
    4721 2135.51    4813 2129.11  4826.6 2130.11  4898.7 2131.54  4941.1 2130.64
  4969.1 2126.68  4977.1 2126.94  4985.3 2125.87  4985.8 2125.37  4997.7 2125.87
  5007.9 2126.22  5013.5 2127.22  5041.5 2137.45  5063.8 2142.05  5116.9 2148.29
#Mann= 3 ,-1 , 0
  4044.7     .07       0  4985.3     .05       0  4997.7     .07       0
Bank Sta=4985.3,4997.7
XS Rating Curve= 0 ,0
Exp/Cntr=0.3,0.1

Type RM Length L Ch R = 1 ,127303  ,438,438,438
BEGIN DESCRIPTION:
Johnson Creek 183.0
END DESCRIPTION:
XS GIS Cut Line= 3
      1818235.82     13974761.26        1818825.       13974475.
      1819099.66      13974229.7
#Sta/Elev= 30
  4336.6 2144.09  4424.6 2140.57  4453.2 2138.11  4774.6 2132.44  4791.5 2130.64
  4797.1 2128.38  4813.8 2126.81  4819.7 2124.96  4842.2 2125.62  4847.8 2127.18
  4870.3 2129.26  4892.9 2129.72  4909.9 2127.96  4932.5 2129.14  4947.2 2127.24
  4969.4 2127.96    4995 2124.73  4999.3  2120.1  4999.8  2119.6  5011.7  2120.1
  5019.7 2122.83  5027.2 2123.77  5062.3 2137.51  5090.7 2143.23  5104.9  2144.8
  5274.6 2155.71  5317.3 2156.19  5324.8 2154.62    5339  2154.3  5359.9 2158.15
#Mann= 3 ,-1 , 0
  4336.6     .07       0  4999.3     .05       0  5011.7     .07       0
Bank Sta=4999.3,5011.7
XS Rating Curve= 0 ,0
Exp/Cntr=0.3,0.1

Type RM Length L Ch R = 1 ,126865  ,432,432,432
BEGIN DESCRIPTION:
Johnson Creek 182.0
END DESCRIPTION:
XS GIS Cut Line= 3
      1818624.98     13975225.02        1819025.       13974825.
      1819424.98       13974825.
#Sta/Elev= 30
  4429.6 2138.29  4528.6 2134.59  4556.9 2132.57  4627.6 2131.48  4655.9 2129.98
  4698.3 2129.25  4740.8    2127  4797.3 2126.05  4839.8 2124.44    4868 2121.75
  4896.3 2125.37    4967 2126.73  4981.2 2125.55  4991.8 2122.75  4997.8 2122.75
    4999 2120.45  4999.5 2119.95  5011.7 2120.45  5015.3 2121.82  5045.3 2123.54
  5055.3 2123.14  5075.3 2124.52  5085.3 2126.46  5175.3 2129.66  5205.3 2132.23
  5255.3 2138.28  5305.3 2141.04  5345.3 2145.62  5365.3 2146.85  5395.3 2147.16
#Mann= 3 ,-1 , 0
  4429.6     .07       0    4999     .05       0  5011.7     .07       0
Bank Sta=4999,5011.7
XS Rating Curve= 0 ,0
Exp/Cntr=0.3,0.1

Type RM Length L Ch R = 1 ,126433  ,436,436,436
BEGIN DESCRIPTION:
Johnson Creek 181.0
END DESCRIPTION:
XS GIS Cut Line= 3
        1818725.       13975425.        1819175.       13975175.
      1819374.98     13974925.03
#Sta/Elev= 30
  4489.2 2140.69  4584.1 2137.43  4621.9 2137.06  4649.4 2134.88  4724.9 2130.75
  4806.1 2123.76  4827.8 2122.85  4843.8 2123.06  4865.6 2121.41  4914.8 2122.68
  4967.8 2118.92  4968.3 2118.42  4980.1 2118.42  4980.6 2118.92  4990.3 2119.55
  5001.1  2123.1    5032 2122.44  5054.4 2120.27  5075.2 2121.42  5081.6 2123.54
  5089.6 2123.93    5096 2127.08    5132 2128.13  5153.7 2129.57  5182.5 2131.66
  5209.7 2134.78  5232.1 2135.62  5316.9  2141.6  5320.9 2143.01  5324.1 2143.01
#Mann= 3 ,-1 , 0
  4489.2     .07       0  4967.8     .05       0  4980.6     .07       0
Bank Sta=4967.8,4980.6
XS Rating Curve= 0 ,0
Exp/Cntr=0.3,0.1

Type RM Length L Ch R = 1 ,125997  ,448,448,448
BEGIN DESCRIPTION:
Johnson Creek 180.0
END DESCRIPTION:
XS GIS Cut Line= 3
      1818774.99       13975525.        1819375.       13975525.
      1819824.97     13974975.03
#Sta/Elev= 30
    4405 2140.83    4515 2135.04    4555 2134.81    4585 2132.78    4645 2132.68
    4685 2130.44    4795 2128.31    4845 2125.56    4905 2117.25    4915 2118.33
    4965 2118.57    4985 2116.68  4996.1  2114.4  4996.6  2113.9  5008.9  2114.4
  5018.6 2116.92  5047.4 2119.65  5069.6 2118.69  5133.5 2123.86  5211.7 2127.26
  5253.4 2131.27  5275.6  2131.4  5366.8  2136.9  5403.4 2137.53  5417.7 2139.45
  5488.1 2141.34    5552 2146.65  5615.9 2149.75    5651 2153.99  5715.6 2158.02
#Mann= 3 ,-1 , 0
    4405     .07       0  4996.1     .05       0  5008.9     .07       0
Bank Sta=4996.1,5008.9
XS Rating Curve= 0 ,0
Exp/Cntr=0.3,0.1

Type RM Length L Ch R = 1 ,125549  ,434,434,434
BEGIN DESCRIPTION:
Johnson Creek 179.0
END DESCRIPTION:
XS GIS Cut Line= 3
        1819475.       13975975.        1819675.       13975825.
      1820274.98     13975225.02
#Sta/Elev= 30
    4750  2131.4  4792.7 2130.76  4821.9 2127.96    4900 2124.88  4928.1 2122.46
    4950 2121.76  4957.3 2119.44  4963.5 2114.68  4979.7 2110.74  4980.2 2110.24
  4993.2 2110.74  5003.5 2110.94  5014.1 2113.58  5028.3 2114.91  5056.6 2115.21
  5141.4    2119  5157.1 2118.98  5268.7 2120.56  5311.1 2122.43  5353.6 2125.74
  5390.4 2130.68  5452.5 2132.53  5551.5 2138.52  5608.1 2139.99  5664.7 2143.01
  5707.1 2147.91  5735.4  2149.9  5802.7 2157.68  5820.2 2160.11  5848.5 2160.63
#Mann= 6 ,-1 , 0
    4750     .07       0  4979.7     .05       0  4993.2     .07       0
  5157.1      .1       0  5390.4     .07       0  5802.7      .1       0
Bank Sta=4979.7,4993.2
XS Rating Curve= 0 ,0
Exp/Cntr=0.3,0.1

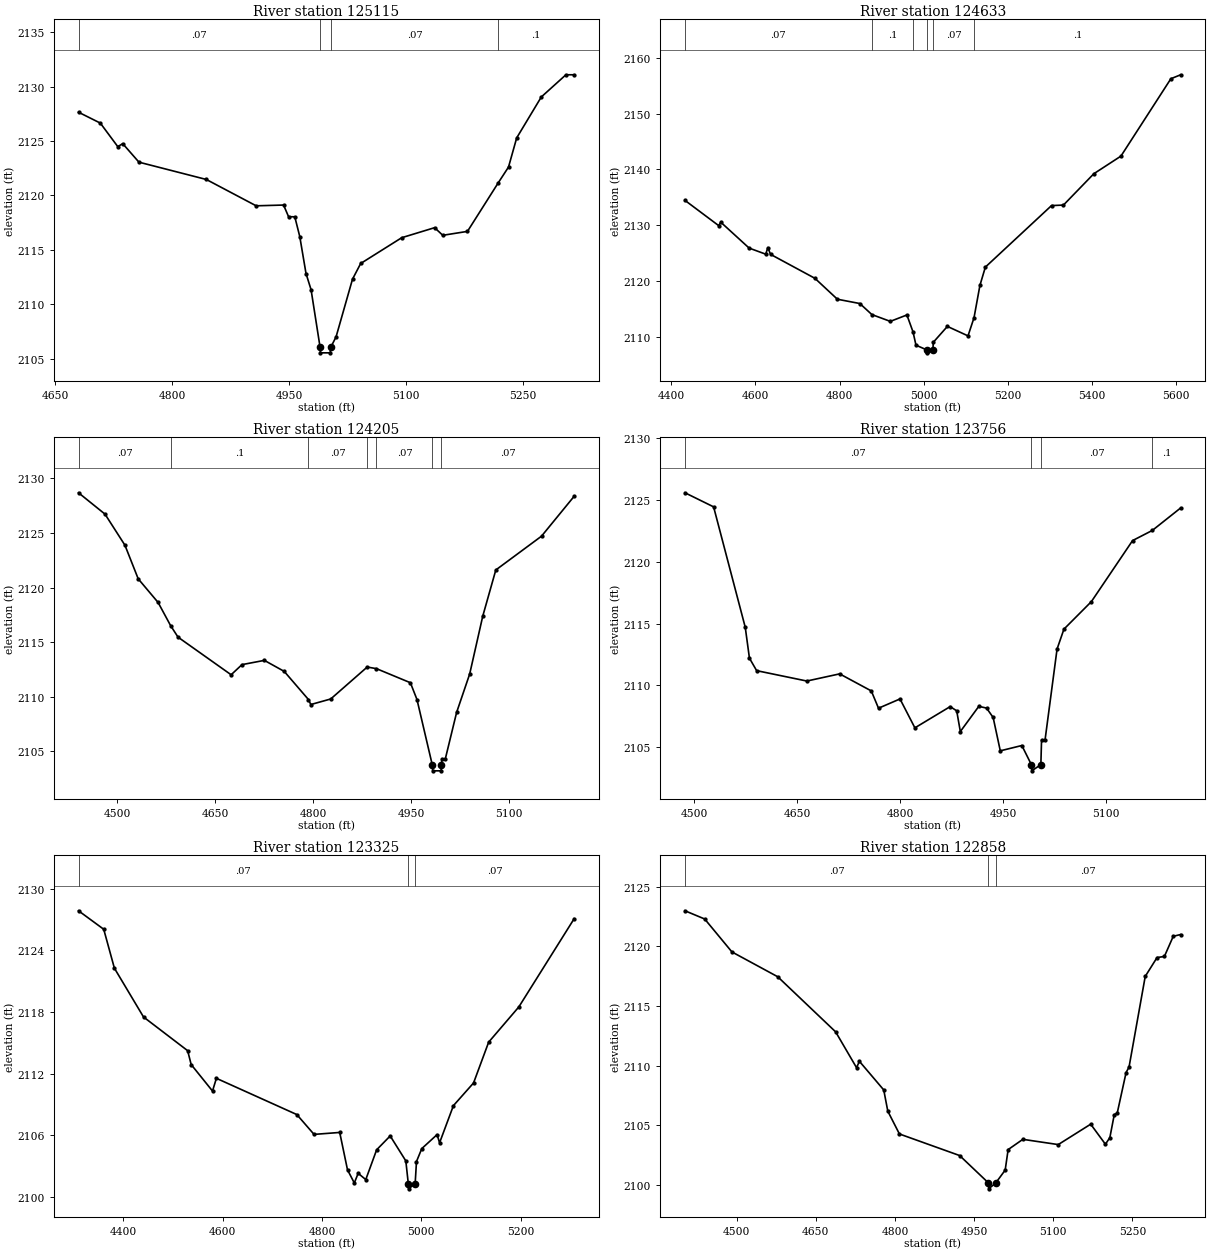
Type RM Length L Ch R = 1 ,125115  ,482,482,482
BEGIN DESCRIPTION:
Johnson Creek 178.0
END DESCRIPTION:
XS GIS Cut Line= 3
        1819875.       13976175.        1820075.       13975925.
        1820175.     13975624.99
#Sta/Elev= 30
  4679.8 2127.65  4707.8 2126.65  4730.2 2124.49  4736.6 2124.76  4757.4 2123.06
  4843.9 2121.47  4907.9 2119.05  4943.1 2119.12  4949.5 2118.05  4957.5 2118.04
  4963.9 2116.22  4971.9 2112.83  4978.4 2111.34    4990 2106.04  4990.5 2105.54
  5003.1 2105.54  5003.6 2106.04  5010.5 2107.01  5031.6 2112.31  5042.1 2113.75
  5094.8 2116.12    5137 2117.04  5147.5 2116.34  5179.2  2116.7  5218.7 2121.16
  5231.9 2122.61  5242.4 2125.29    5274 2129.05  5305.6 2131.09  5316.2 2131.09
#Mann= 4 ,-1 , 0
  4679.8     .07       0    4990     .05       0  5003.6     .07       0
  5218.7      .1       0
Bank Sta=4990,5003.6
XS Rating Curve= 0 ,0
Exp/Cntr=0.3,0.1

Type RM Length L Ch R = 1 ,124633  ,428,428,428
BEGIN DESCRIPTION:
Johnson Creek 177.0
END DESCRIPTION:
XS GIS Cut Line= 3
      1820425.01     13976574.97        1820525.       13976025.
      1820675.01     13975424.95
#Sta/Elev= 30
  4432.9 2134.45  4512.9 2129.93    4518 2130.54  4585.3  2125.9  4624.7 2124.81
  4629.8 2125.99  4636.1 2124.78  4741.6 2120.48    4795 2116.73  4848.3 2115.96
  4876.9 2113.98  4920.7 2112.76  4960.1 2113.91  4974.6 2110.89  4981.7 2108.49
  5008.2 2107.62  5008.7 2107.12  5021.9 2107.62  5022.8 2109.01  5056.3 2111.86
  5105.3 2110.16  5119.6 2113.43  5133.6 2119.22  5146.5 2122.49  5303.7 2133.52
    5332 2133.61  5404.2 2139.23  5468.6 2142.39  5587.2 2156.26  5610.4 2156.97
#Mann= 6 ,-1 , 0
  4432.9     .07       0  4876.9      .1       0  4974.6     .07       0
  5008.2     .05       0  5021.9     .07       0  5119.6      .1       0
Bank Sta=5008.2,5021.9
XS Rating Curve= 0 ,0
Exp/Cntr=0.3,0.1

Type RM Length L Ch R = 1 ,124205  ,449,449,449
BEGIN DESCRIPTION:
Johnson Creek 176.0
END DESCRIPTION:
XS GIS Cut Line= 3
      1820825.01     13976574.97        1820925.       13976025.
        1820925.     13975824.98
#Sta/Elev= 30
  4440.7 2128.69  4481.3 2126.73  4511.8 2123.88  4532.1  2120.8  4562.6 2118.63
  4581.7 2116.51  4593.1 2115.45  4674.4    2112    4691 2112.93  4725.3 2113.32
  4755.7 2112.31  4792.8 2109.73  4796.4 2109.27  4826.9 2109.78  4882.8 2112.71
    4897 2112.56  4948.9 2111.27    4959 2109.73  4982.6 2103.69  4983.1 2103.19
  4995.9 2103.19  4996.4 2103.69  4997.1 2104.24  5002.2 2104.24  5019.7 2108.55
  5039.7 2112.07  5059.7 2117.37  5079.7 2121.61  5149.7 2124.71  5199.7 2128.37
#Mann= 7 ,-1 , 0
  4440.7     .07       0  4581.7      .1       0  4792.8     .07       0
  4882.8      .1       0    4897     .07       0  4982.6     .05       0
  4996.4     .07       0
Bank Sta=4982.6,4996.4
XS Rating Curve= 0 ,0
Exp/Cntr=0.3,0.1

Type RM Length L Ch R = 1 ,123756  ,431,431,431
BEGIN DESCRIPTION:
Johnson Creek 175.0
END DESCRIPTION:
XS GIS Cut Line= 3
      1821175.01     13976574.97        1821325.       13976075.
        1821325.     13975874.99
#Sta/Elev= 30
  4486.3  2125.6    4528 2124.46  4574.1 2114.71  4580.2 2112.21  4590.7  2111.2
  4663.8 2110.36  4711.6 2110.94  4757.7 2109.56  4768.2 2108.16  4799.5 2108.91
  4821.2 2106.57  4872.6 2108.29  4882.1 2107.95  4887.4 2106.27  4914.3 2108.31
  4925.6 2108.17  4935.2 2107.41  4945.6 2104.71    4977 2105.14  4990.9 2103.59
  4991.4 2103.09  5004.7 2103.59  5005.7 2105.59  5010.8 2105.59  5028.3 2112.95
  5038.3 2114.56  5078.3 2116.79  5138.3 2121.73    5167 2122.55  5208.3 2124.37
#Mann= 4 ,-1 , 0
  4486.3     .07       0  4990.9     .05       0  5004.7     .07       0
    5167      .1       0
Bank Sta=4990.9,5004.7
XS Rating Curve= 0 ,0
Exp/Cntr=0.3,0.1

Type RM Length L Ch R = 1 ,123325  ,467,467,467
BEGIN DESCRIPTION:
Johnson Creek 174.0
END DESCRIPTION:
XS GIS Cut Line= 3
      1821375.01     13976774.98        1821725.       13976175.
      1821774.99     13975875.03
#Sta/Elev= 30
  4309.4 2127.86  4360.2 2126.06  4381.7 2122.27  4440.4 2117.52  4529.3 2114.24
  4536.4 2112.89  4579.4 2110.31  4587.2 2111.55  4749.3 2108.02    4784 2106.09
  4835.7 2106.28  4851.4 2102.64  4865.1 2101.36  4872.9  2102.3  4888.2 2101.69
  4910.1 2104.59  4937.4 2105.94  4968.9 2103.51  4973.9 2101.29  4974.4 2100.79
  4987.7 2101.29  4990.4 2103.45  5001.1 2104.71  5031.9 2106.07  5036.9 2105.27
  5064.8 2108.89  5105.4  2111.1  5135.8 2115.07  5196.6  2118.5  5308.1 2127.09
#Mann= 3 ,-1 , 0
  4309.4     .07       0  4973.9     .05       0  4987.7     .07       0
Bank Sta=4973.9,4987.7
XS Rating Curve= 0 ,0
Exp/Cntr=0.3,0.1

Type RM Length L Ch R = 1 ,122858  ,582,582,582
BEGIN DESCRIPTION:
Johnson Creek 173.0
END DESCRIPTION:
XS GIS Cut Line= 3
      1821874.99     13976825.02        1822125.       13976275.
      1821974.99     13975974.99
#Sta/Elev= 30
    4402 2122.98  4439.4 2122.29    4491 2119.53  4577.8 2117.45  4687.6 2112.83
  4727.2 2109.83  4732.7 2110.36  4778.8 2107.96  4786.5 2106.18  4808.5 2104.27
  4922.7 2102.46  4977.2 2100.17  4977.7 2099.67  4991.2 2100.17    5009 2101.24
  5014.6 2102.96  5042.5 2103.82  5109.6 2103.38  5171.1 2105.09    5199 2103.41
  5207.4 2103.96  5215.8 2105.89  5221.4 2106.02  5238.2 2109.42  5243.8 2109.88
  5274.5 2117.48  5296.9 2119.06  5310.8 2119.15  5327.6 2120.84  5341.6 2120.99
#Mann= 3 ,-1 , 0
    4402     .07       0  4977.2     .05       0  4991.2     .07       0
Bank Sta=4977.2,4991.2
XS Rating Curve= 0 ,0
Exp/Cntr=0.3,0.1

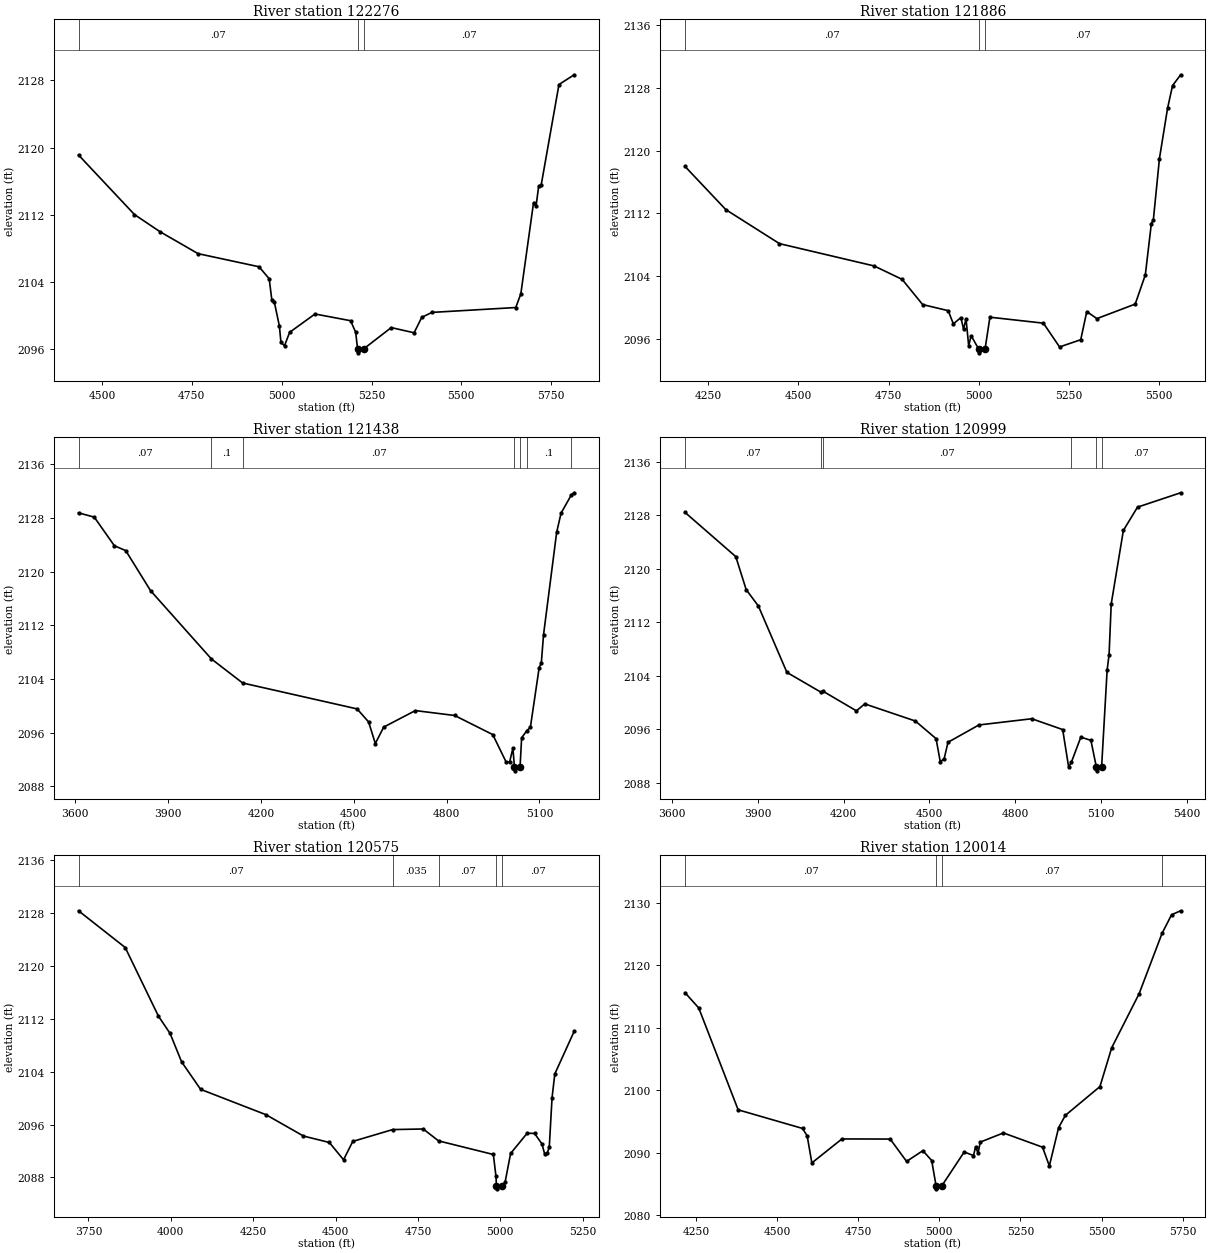
Type RM Length L Ch R = 1 ,122276  ,390,390,390
BEGIN DESCRIPTION:
Johnson Creek 172.0
END DESCRIPTION:
XS GIS Cut Line= 3
      1822224.98     13976875.02      1822605.74     13976457.49
      1823174.97     13975875.03
#Sta/Elev= 30
  4434.5 2119.12  4590.3 2112.02  4661.2 2109.98  4767.3 2107.36  4936.9  2105.8
  4965.2 2104.37  4972.7 2101.79  4979.4 2101.62  4993.6 2098.72  4997.9 2096.78
  5007.9 2096.39    5022 2097.98  5092.7 2100.17  5191.7 2099.37  5205.9 2097.99
  5211.1 2096.04  5211.6 2095.54    5229 2096.04  5304.9 2098.55  5368.5 2097.93
  5389.8 2099.77  5418.1 2100.36  5651.4 2100.94  5665.5 2102.56    5701 2113.45
    5708 2113.05  5715.1 2115.37  5722.1 2115.51  5771.7 2127.52    5814 2128.68
#Mann= 3 ,-1 , 0
  4434.5     .07       0  5211.1     .05       0    5229     .07       0
Bank Sta=5211.1,5229
XS Rating Curve= 0 ,0
Exp/Cntr=0.3,0.1

Type RM Length L Ch R = 1 ,121886  ,448,448,448
BEGIN DESCRIPTION:
Johnson Creek 171.0
END DESCRIPTION:
XS GIS Cut Line= 3
      1822424.98     13977025.02        1822975.       13976425.
      1823225.01     13975924.99
#Sta/Elev= 30
  4186.1    2118  4299.3 2112.49  4447.9 2108.16  4709.9 2105.32  4787.6 2103.61
  4844.4  2100.4  4915.3 2099.62  4929.5 2097.94  4950.4 2098.74  4957.8 2097.26
  4964.6 2098.59    4972 2095.15  4978.8 2096.43  4999.5 2094.75    5000 2094.25
  5017.4 2094.75  5030.8 2098.79    5179 2098.03  5223.7    2095  5282.4 2095.92
  5299.1 2099.51  5327.1 2098.61  5433.3 2100.46  5461.3 2104.18    5478 2110.72
  5483.6 2111.21  5500.4    2119  5522.8 2125.38  5536.7 2128.29  5559.1 2129.67
#Mann= 3 ,-1 , 0
  4186.1     .07       0  4999.5     .05       0  5017.4     .07       0
Bank Sta=4999.5,5017.4
XS Rating Curve= 0 ,0
Exp/Cntr=0.3,0.1

Type RM Length L Ch R = 1 ,121438  ,439,439,439
BEGIN DESCRIPTION:
Johnson Creek 170.0
END DESCRIPTION:
XS GIS Cut Line= 3
      1822624.99     13977475.02        1823325.       13976275.
        1823475.       13976125.
#Sta/Elev= 30
  3610.7 2128.77  3661.6 2128.13  3726.5 2123.87  3763.3 2123.14  3843.5 2117.17
  4040.2 2106.99    4141 2103.41  4510.8 2099.55  4548.1  2097.6  4569.6 2094.39
  4596.8 2096.84    4699  2099.3  4825.9 2098.57  4949.1 2095.72  4992.1 2091.65
  5003.5 2091.62  5014.1  2093.7  5019.3 2090.82  5019.8 2090.32  5037.2 2090.82
  5042.4 2095.25  5058.6 2096.27  5070.7 2096.82    5099 2105.69    5106 2106.39
  5113.1 2110.59  5155.5 2125.86  5169.7 2128.72  5202.8 2131.43  5212.1 2131.76
#Mann= 7 ,-1 , 0
  3610.7     .07       0  4040.2      .1       0    4141     .07       0
  5019.3     .05       0  5037.2     .07       0  5058.6      .1       0
  5202.8     .07       0
Bank Sta=5019.3,5037.2
XS Rating Curve= 0 ,0
Exp/Cntr=0.3,0.1

Type RM Length L Ch R = 1 ,120999  ,424,424,424
BEGIN DESCRIPTION:
Johnson Creek 169.0
END DESCRIPTION:
XS GIS Cut Line= 3
        1822775.       13977575.      1823598.33     13976497.34
      1823850.61     13976217.56
#Sta/Elev= 30
  3645.6 2128.42  3823.3  2121.8  3859.5 2116.87  3902.2 2114.42    4002 2104.49
  4120.2 2101.55  4129.2 2101.65  4245.1 2098.74  4274.1 2099.78    4451 2097.22
  4523.5 2094.58  4538.1 2091.13  4551.7 2091.58  4565.2 2094.04  4673.2 2096.63
  4858.1 2097.56  4966.1 2095.94  4986.9 2090.35  4996.2 2091.02  5029.6 2094.81
  5064.8 2094.33  5084.2 2090.27  5084.7 2089.77  5102.1 2090.27  5121.6 2104.88
  5128.3 2107.12  5135.8 2114.72  5178.3 2125.72  5227.7  2129.2  5378.5 2131.35
#Mann= 6 ,-1 , 0
  3645.6     .07       0  4120.2      .1       0  4129.2     .07       0
  4996.2      .1       0  5084.2     .05       0  5102.1     .07       0
Bank Sta=5084.2,5102.1
XS Rating Curve= 0 ,0
Exp/Cntr=0.3,0.1

Type RM Length L Ch R = 1 ,120575  ,561,561,561
BEGIN DESCRIPTION:
Johnson Creek 168.0
END DESCRIPTION:
XS GIS Cut Line= 3
      1822824.98     13977575.02        1823825.       13976775.
      1824025.04     13976674.98
#Sta/Elev= 30
  3719.9 2128.36  3861.6  2122.8  3962.4 2112.42  3997.7  2109.8  4032.9 2105.48
  4090.5 2101.33    4289 2097.49  4402.7 2094.26  4481.1 2093.29  4524.3 2090.67
  4552.3 2093.45  4673.3 2095.24    4766 2095.33  4812.6 2093.53  4978.9 2091.47
  4986.9 2088.16  4988.3 2086.77  4988.8 2086.27  5006.3 2086.77  5014.5 2087.26
  5031.3 2091.62  5081.6 2094.69    5104 2094.66  5126.3 2093.08  5134.7 2091.54
  5143.1 2091.75  5148.7 2092.62  5157.1 2100.08  5165.5 2103.67  5224.2 2110.11
#Mann= 5 ,-1 , 0
  3719.9     .07       0  4673.3    .035       0  4812.6     .07       0
  4988.3     .05       0  5006.3     .07       0
Bank Sta=4988.3,5006.3
XS Rating Curve= 0 ,0
Exp/Cntr=0.3,0.1

Type RM Length L Ch R = 1 ,120014  ,321,321,321
BEGIN DESCRIPTION:
Johnson Creek 167.0
END DESCRIPTION:
XS GIS Cut Line= 3
      1823274.98     13977775.01      1823928.27     13977244.74
      1824375.03     13976724.97
#Sta/Elev= 30
  4216.6  2115.6    4259 2113.15  4380.4 2096.84  4578.7 2093.86    4593 2092.67
  4607.4 2088.34  4700.1 2092.18  4848.8 2092.16  4899.2 2088.58  4949.4  2090.3
  4976.6 2088.72    4990 2084.69  4990.5 2084.19    5008 2084.69  5076.7 2090.09
  5105.3 2089.52  5111.8  2090.9  5119.5  2089.9  5126.1 2091.67  5197.4 2093.14
  5318.1 2090.86    5339 2087.85  5367.5 2093.99  5388.4 2095.96  5494.8 2100.56
    5531 2106.77  5615.5 2115.43  5686.2  2125.1  5715.4 2128.07  5743.4 2128.71
#Mann= 4 ,-1 , 0
  4216.6     .07       0    4990     .05       0    5008     .07       0
  5686.2      .1       0
Bank Sta=4990,5008
XS Rating Curve= 0 ,0
Exp/Cntr=0.3,0.1

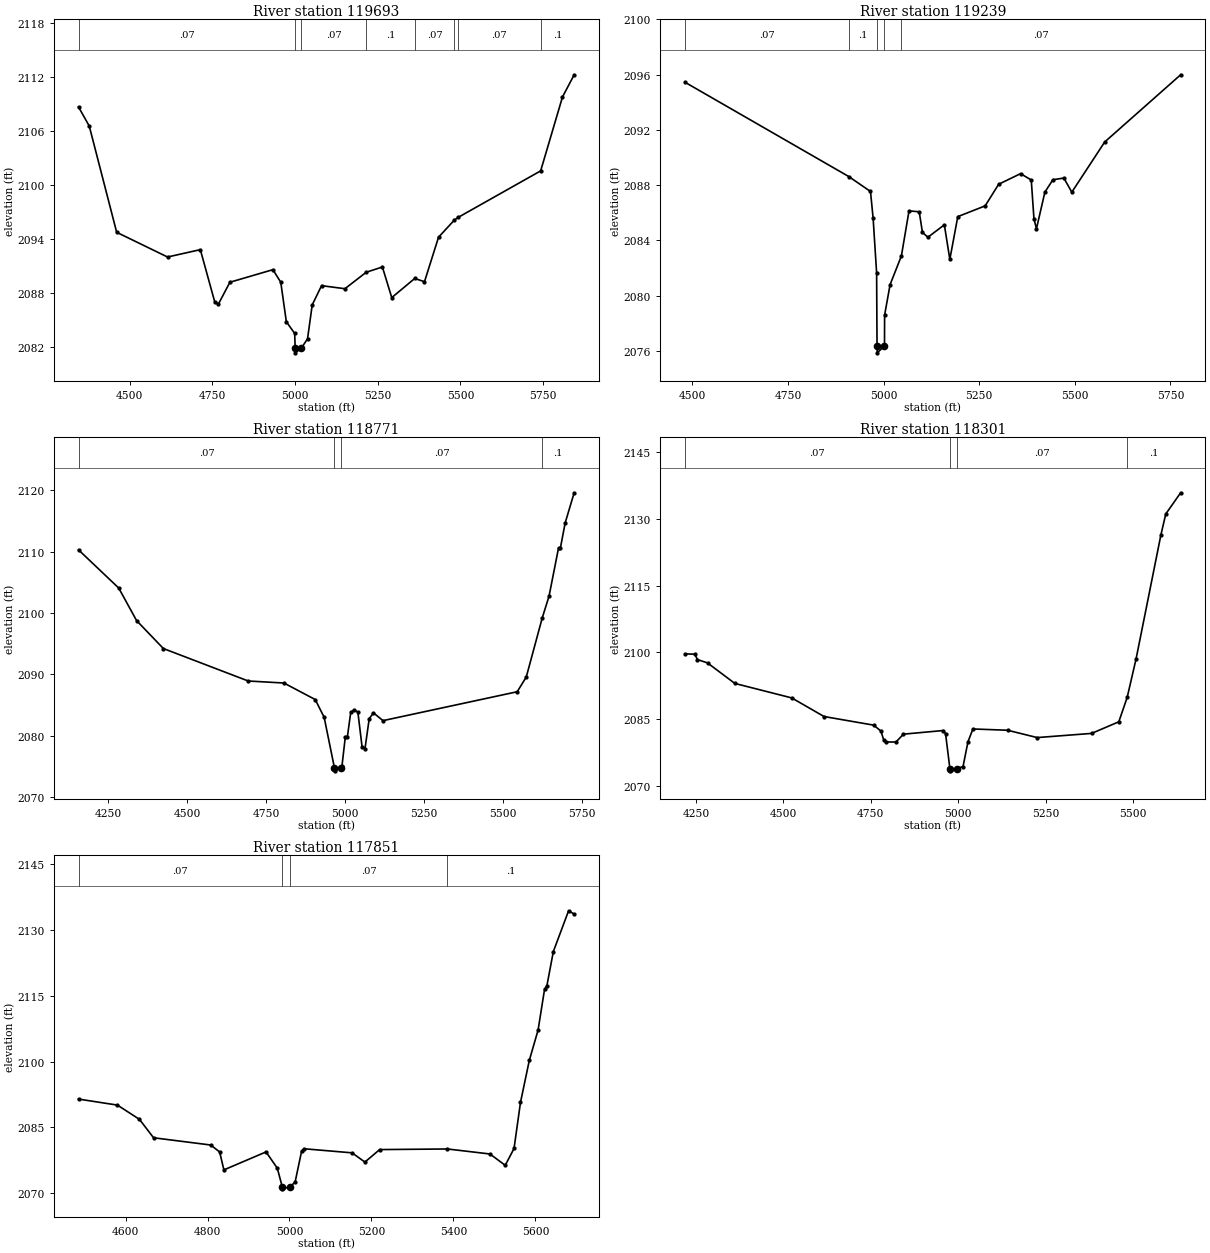
Type RM Length L Ch R = 1 ,119693  ,454,454,454
BEGIN DESCRIPTION:
Johnson Creek 166.0
END DESCRIPTION:
XS GIS Cut Line= 3
      1823375.01     13977824.99        1823975.       13977575.
      1824574.99     13976975.01
#Sta/Elev= 30
  4345.5 2108.68    4378 2106.55  4460.9 2094.72  4614.7 2091.97  4713.8 2092.79
  4757.2 2086.99    4768  2086.7  4803.2 2089.16  4933.2 2090.56    4957 2089.16
  4973.8 2084.77    4999 2083.46  5000.6  2081.8  5001.1  2081.3  5018.7  2081.8
  5037.9 2082.86  5052.1 2086.64  5080.3 2088.78    5151 2088.44  5215.2 2090.27
  5264.2 2090.86  5292.5 2087.45    5362 2089.58  5391.5 2089.22  5433.9 2094.17
  5481.7 2096.08  5492.7 2096.37  5742.7 2101.56  5808.7 2109.79    5844 2112.26
#Mann= 8 ,-1 , 0
  4345.5     .07       0  5000.6     .05       0  5018.7     .07       0
  5215.2      .1       0    5362     .07       0  5481.7      .1       0
  5492.7     .07       0  5742.7      .1       0
Bank Sta=5000.6,5018.7
XS Rating Curve= 0 ,0
Exp/Cntr=0.3,0.1

Type RM Length L Ch R = 1 ,119239  ,468,468,468
BEGIN DESCRIPTION:
Johnson Creek 165.0
END DESCRIPTION:
XS GIS Cut Line= 3
      1823875.02     13978424.96        1824125.       13977975.
      1824625.02     13977374.97
#Sta/Elev= 30
  4480.8 2095.44    4909 2088.62  4965.8 2087.54  4972.7  2085.6  4981.8 2081.65
  4982.9 2076.37  4983.4 2075.87  5002.4 2076.37  5002.7  2078.6    5017  2080.8
  5046.6 2082.88  5066.5 2086.14  5093.2 2086.07  5101.6 2084.58  5115.9 2084.23
  5158.9 2085.13  5173.2 2082.63    5194 2085.72  5265.6  2086.5  5300.8 2088.06
  5358.1 2088.83  5386.1 2088.37  5393.2 2085.54  5399.7 2084.85  5421.8  2087.5
  5442.7 2088.39  5471.3 2088.51  5492.1 2087.49  5578.1 2091.12  5776.6 2095.98
#Mann= 5 ,-1 , 0
  4480.8     .07       0    4909      .1       0  4982.9     .05       0
  5002.4      .1       0  5046.6     .07       0
Bank Sta=4982.9,5002.4
XS Rating Curve= 0 ,0
Exp/Cntr=0.3,0.1

Type RM Length L Ch R = 1 ,118771  ,470,470,470
BEGIN DESCRIPTION:
Johnson Creek 164.0
END DESCRIPTION:
XS GIS Cut Line= 3
      1823925.02     13978774.98        1824525.       13978175.
      1825124.99     13977775.01
#Sta/Elev= 30
  4156.1  2110.3  4283.4 2104.08  4339.9 2098.78  4424.8 2094.22  4693.5 2088.93
  4806.6  2088.6  4905.6 2085.91  4933.9 2083.03  4966.5 2074.79    4967 2074.29
  4986.1 2074.79  4990.5 2075.13  5001.1 2079.86  5007.6 2079.86  5018.1  2083.8
  5027.1 2084.17  5040.7  2083.9  5054.2 2078.13  5063.2 2077.87  5076.7 2082.79
  5090.2 2083.74  5120.3 2082.47  5545.4 2087.18    5574 2089.58  5624.9 2099.26
  5646.1 2102.75  5676.1 2110.58  5682.2 2110.63  5697.2 2114.69  5725.7  2119.6
#Mann= 4 ,-1 , 0
  4156.1     .07       0  4966.5     .05       0  4986.1     .07       0
  5624.9      .1       0
Bank Sta=4966.5,4986.1
XS Rating Curve= 0 ,0
Exp/Cntr=0.3,0.1

Type RM Length L Ch R = 1 ,118301  ,450,450,450
BEGIN DESCRIPTION:
Johnson Creek 163.0
END DESCRIPTION:
XS GIS Cut Line= 3
      1824274.96     13978975.03        1824875.       13978475.
      1825325.02     13978024.98
#Sta/Elev= 30
  4218.7 2099.65  4246.7 2099.57  4254.5 2098.36  4283.2 2097.61  4361.3 2092.99
    4524 2089.73  4616.4 2085.54  4758.3  2083.6  4779.1 2082.26  4786.9  2080.3
  4793.5 2079.81  4822.1  2079.8  4843.6 2081.57  4957.5 2082.39    4964 2081.64
  4976.3 2073.81  4976.8 2073.31  4995.9 2073.81  5013.9 2074.28  5028.1 2079.88
  5042.2 2082.74  5141.2 2082.45    5226  2080.8  5381.6 2081.74  5459.4 2084.35
  5483.4 2089.87  5508.9 2098.56  5579.6 2126.37  5593.7 2131.15  5636.2 2135.92
#Mann= 4 ,-1 , 0
  4218.7     .07       0  4976.3     .05       0  4995.9     .07       0
  5483.4      .1       0
Bank Sta=4976.3,4995.9
XS Rating Curve= 0 ,0
Exp/Cntr=0.3,0.1

Type RM Length L Ch R = 1 ,117851  ,471,471,471
BEGIN DESCRIPTION:
Johnson Creek 162.0
END DESCRIPTION:
XS GIS Cut Line= 3
      1824574.97     13979125.02        1825025.       13978875.
      1825624.97     13978525.02
#Sta/Elev= 30
  4485.2 2091.46  4580.2 2090.09    4634 2086.84  4668.3 2082.66  4807.8 2081.01
  4829.6 2079.43  4839.9 2075.35  4942.8 2079.44  4970.3 2075.73  4982.2 2071.54
  4982.7 2071.04  5001.8 2071.54  5013.7 2072.59  5029.4 2079.54  5035.2 2080.16
  5152.6 2079.23    5184 2077.13    5220 2079.97  5385.2 2080.11  5489.1 2078.97
  5526.4 2076.39  5547.9 2080.22  5563.6  2090.7  5585.1 2100.24  5606.6 2107.18
  5622.3 2116.41  5628.1 2117.27  5643.8 2125.03    5681  2134.3  5694.6 2133.55
#Mann= 4 ,-1 , 0
  4485.2     .07       0  4982.2     .05       0  5001.8     .07       0
  5385.2      .1       0
Bank Sta=4982.2,5001.8
XS Rating Curve= 0 ,0
Exp/Cntr=0.3,0.1