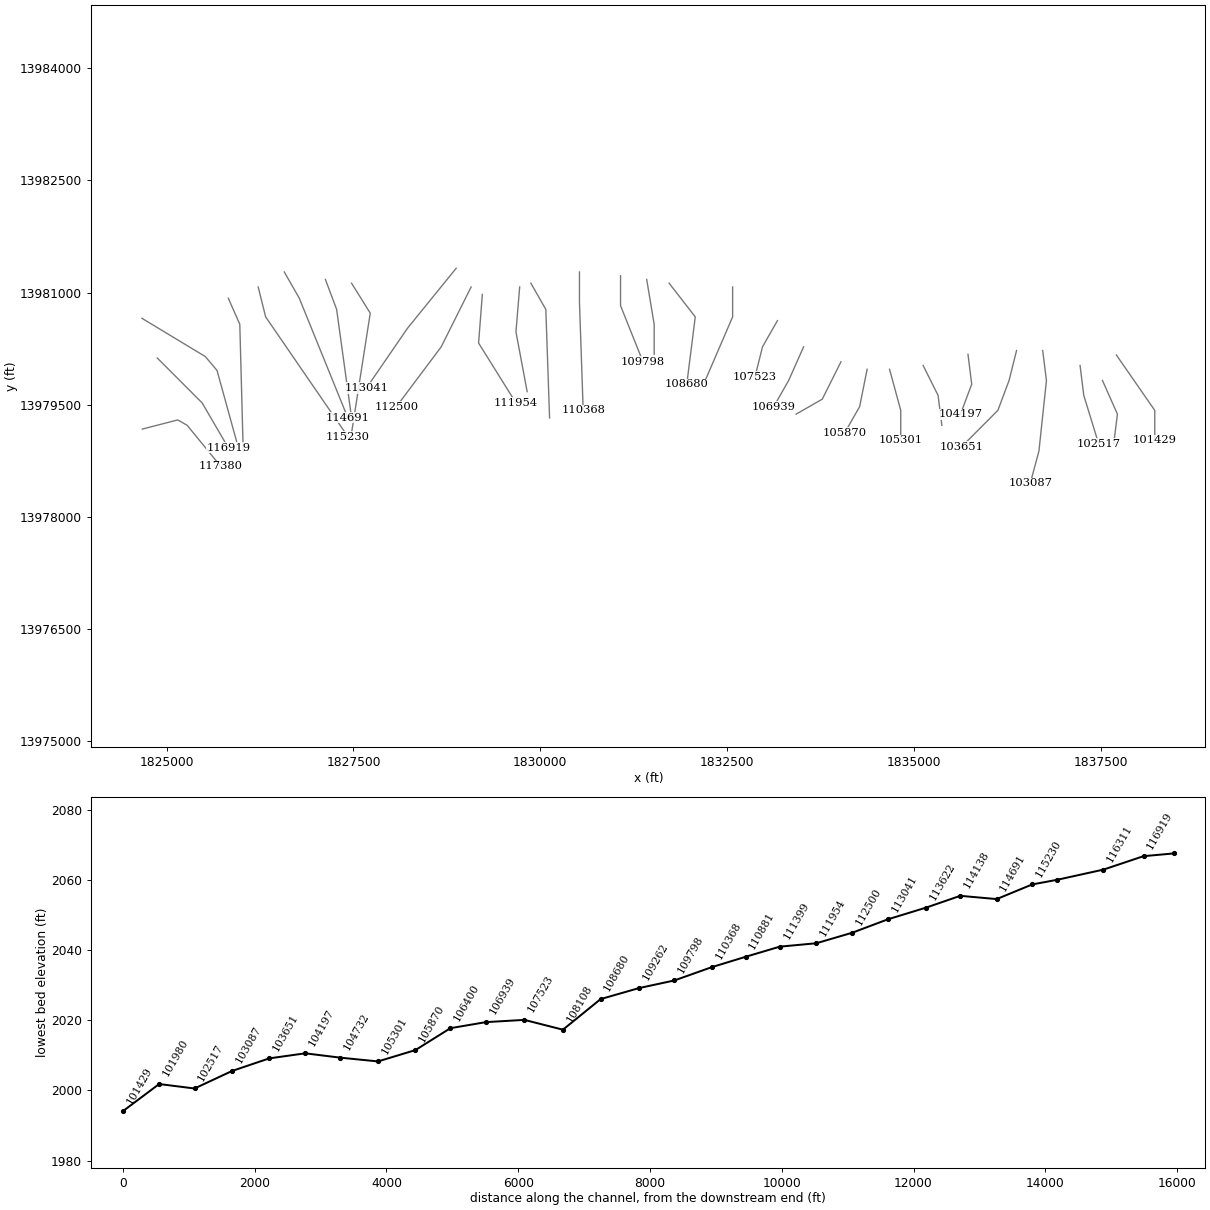
HEC-RAS study Johnson Creek.prj: Johnson Creek Base Level Engineering

--- Johnson Creek.g01 (geometry) --- (continued)

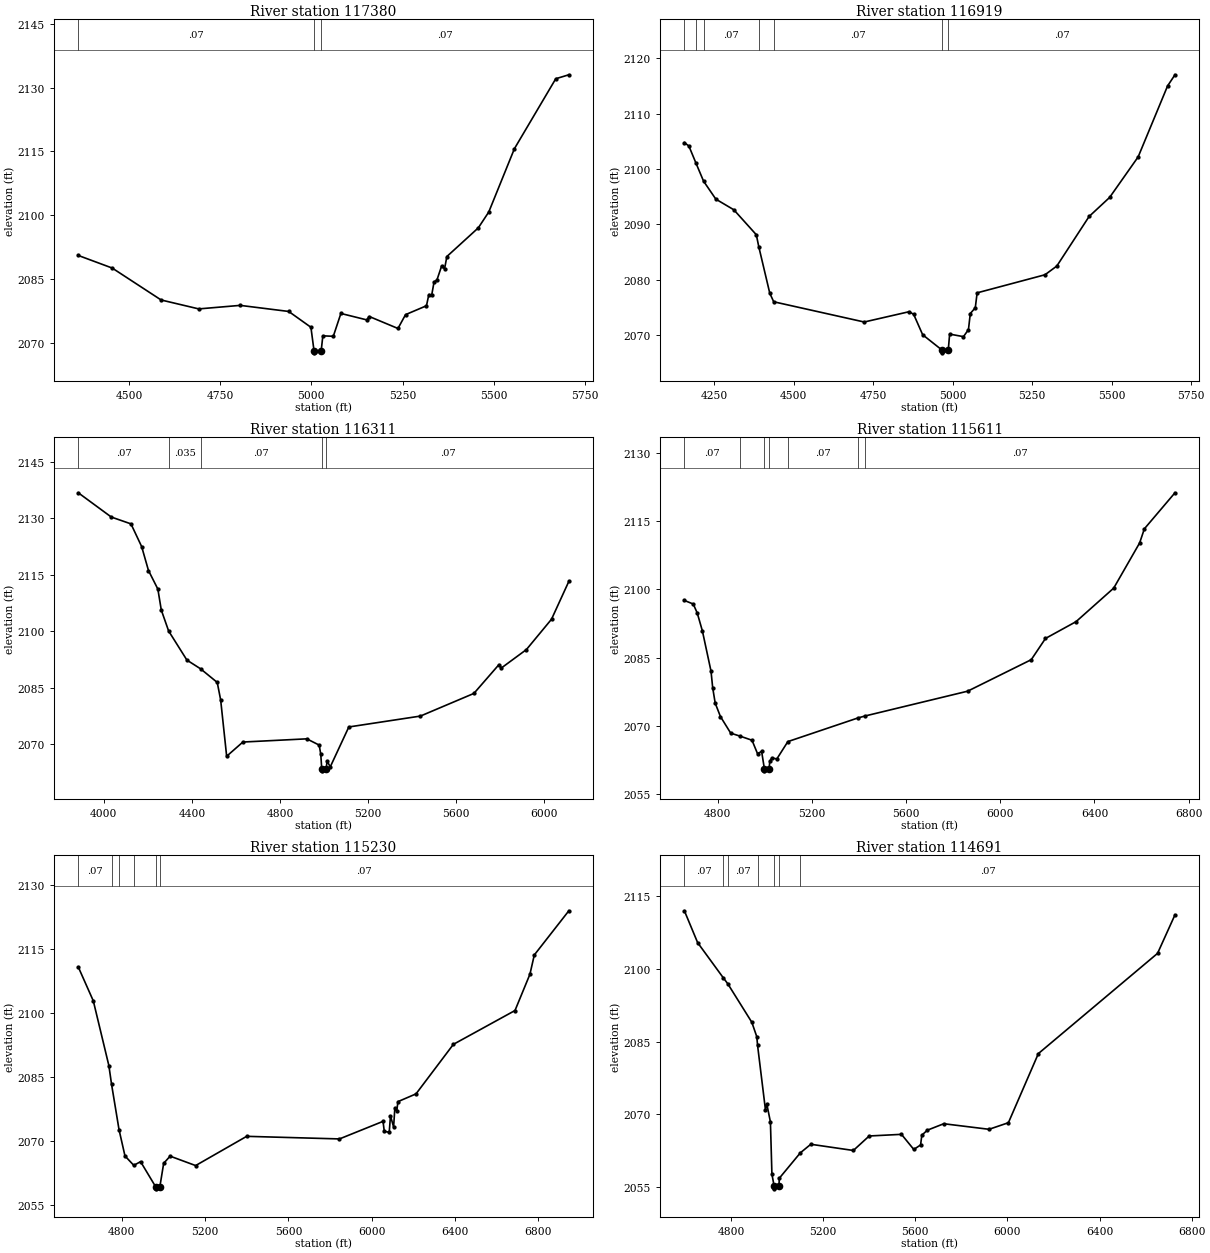
Type RM Length L Ch R = 1 ,117380  ,461,461,461
BEGIN DESCRIPTION:
Johnson Creek 161.0
END DESCRIPTION:
XS GIS Cut Line= 4
      1824674.98     13979174.99      1825148.85     13979297.41
        1825275.       13979225.      1825724.99     13978675.01
#Sta/Elev= 30
  4360.7 2090.53  4453.7 2087.57  4587.9 2080.06  4691.2 2077.96  4804.8 2078.79
  4937.9 2077.36  4998.8 2073.64  5007.3 2068.13  5007.8 2067.63    5027 2068.13
  5031.5 2071.63  5060.2 2071.52    5081 2076.89  5151.4 2075.39  5159.2 2076.16
  5237.5 2073.36  5258.3 2076.61  5315.7  2078.7  5322.2 2081.33  5330.1 2081.23
  5336.5  2084.3  5344.4 2084.76  5357.4 2088.08  5365.3 2087.37  5371.7 2090.28
  5457.9 2097.02  5486.6 2100.75  5556.9 2115.63  5670.3 2132.08  5706.2 2133.01
#Mann= 3 ,-1 , 0
  4360.7     .07       0  5007.3     .05       0    5027     .07       0
Bank Sta=5007.3,5027
XS Rating Curve= 0 ,0
Exp/Cntr=0.3,0.1

Type RM Length L Ch R = 1 ,116919  ,608,608,608
BEGIN DESCRIPTION:
Johnson Creek 160.0
END DESCRIPTION:
XS GIS Cut Line= 3
      1824874.98     13980125.02        1825475.       13979525.
      1825825.01     13978924.98
#Sta/Elev= 30
  4155.8 2104.76    4170 2104.14  4191.8 2101.12  4216.2  2097.8  4254.8 2094.56
  4311.4 2092.64  4382.1 2088.14  4389.8 2085.99  4424.5 2077.58  4436.8 2076.05
  4721.5  2072.4  4862.9 2074.26  4877.1 2073.78  4905.4  2070.1  4966.2 2067.34
  4966.7 2066.84  4985.9 2067.34  4990.2 2070.22  5033.7 2069.76  5049.4 2071.03
  5055.2 2073.93  5070.9 2074.97  5076.7 2077.66  5290.1 2080.92  5327.3 2082.49
    5429 2091.44  5493.5 2094.87  5583.2 2102.18  5675.8 2114.98    5699 2116.99
#Mann= 7 ,-1 , 0
  4155.8     .07       0  4191.8    .035       0  4216.2     .07       0
  4389.8    .035       0  4436.8     .07       0  4966.2     .05       0
  4985.9     .07       0
Bank Sta=4966.2,4985.9
XS Rating Curve= 0 ,0
Exp/Cntr=0.3,0.1

Type RM Length L Ch R = 1 ,116311  ,700,700,700
BEGIN DESCRIPTION:
Johnson Creek 159.1
END DESCRIPTION:
XS GIS Cut Line= 4
       1824669.2     13980656.26       1825517.3     13980144.74
      1825674.34     13979959.13      1825939.18     13978999.04
#Sta/Elev= 30
  3883.6 2136.78  4033.8 2130.34  4123.1 2128.53  4171.6 2122.52  4202.7 2116.16
  4245.4 2111.22  4260.9 2105.68  4294.3 2100.11  4377.4 2092.39  4439.4 2090.08
  4515.2 2086.47  4530.8  2081.8    4558 2066.88  4631.7 2070.65  4922.1  2071.5
  4978.5 2069.84  4985.8 2067.37    4990 2063.51  4990.5 2063.01  5010.2 2063.51
  5014.4 2065.65  5028.7 2064.05  5113.2 2074.65  5438.6 2077.54  5681.6 2083.55
  5795.7 2091.21  5806.1 2090.28  5920.2 2095.18  6034.3 2103.23  6113.1 2113.28
#Mann= 5 ,-1 , 0
  3883.6     .07       0  4294.3    .035       0  4439.4     .07       0
    4990     .05       0  5010.2     .07       0
Bank Sta=4990,5010.2
XS Rating Curve= 0 ,0
Exp/Cntr=0.3,0.1

Type RM Length L Ch R = 1 ,115611  ,381,381,381
BEGIN DESCRIPTION:
Johnson Creek 159.0
END DESCRIPTION:
XS GIS Cut Line= 3
        1825825.     13980925.01      1825978.95     13980576.34
        1826025.     13978875.01
#Sta/Elev= 30
  4658.6 2097.59  4696.3  2096.8  4713.3 2094.82  4735.1 2090.88  4771.7 2082.04
  4778.9 2078.36  4789.5    2075  4811.7 2072.05  4855.4  2068.4  4896.4 2067.72
  4945.8 2066.84  4969.1  2063.9  4986.6 2064.38  4998.2 2060.61  4998.7 2060.11
  5018.6 2060.61  5021.2 2062.19  5030.3 2062.96  5051.1 2062.72    5098 2066.54
  5395.4 2071.74  5426.3 2072.18  5861.4 2077.63  6131.5 2084.56  6191.9 2089.23
  6321.6 2092.92  6481.6  2100.3  6591.7 2110.24  6611.7 2113.34  6741.7 2121.27
#Mann= 7 ,-1 , 0
  4658.6     .07       0  4896.4     .07       0  4998.2     .05       0
  5018.6     .07       0    5098     .07       0  5395.4    .035       0
  5426.3     .07       0
Bank Sta=4998.2,5018.6
XS Rating Curve= 0 ,0
Exp/Cntr=0.3,0.1

Type RM Length L Ch R = 1 ,115230  ,539,539,539
BEGIN DESCRIPTION:
Johnson Creek 158.0
END DESCRIPTION:
XS GIS Cut Line= 3
      1826224.99     13981075.04        1826325.       13980675.
        1827425.       13979075.
#Sta/Elev= 30
  4591.8 2110.84    4664 2102.88  4738.7 2087.69  4751.6  2083.3  4787.5 2072.65
    4816 2066.49  4858.3 2064.29  4890.8 2065.16    4963 2059.28  4963.5 2058.78
  4983.4 2059.28  5001.6 2064.76  5032.6 2066.45    5155 2064.24  5399.9  2071.1
  5845.1 2070.49  6054.1 2074.61  6060.2 2072.28  6083.9 2072.05    6090  2075.9
  6104.9 2073.29  6110.9 2077.74  6119.8 2077.01  6125.8 2079.24  6212.4 2081.06
  6391.7 2092.68  6687.4 2100.62  6759.1 2109.14    6780 2113.65  6945.8 2124.02
#Mann= 6 ,-1 , 0
  4591.8     .07       0  4751.6    .035       0  4787.5     .07       0
  4858.3     .07       0    4963     .05       0  4983.4     .07       0
Bank Sta=4963,4983.4
XS Rating Curve= 0 ,0
Exp/Cntr=0.3,0.1

Type RM Length L Ch R = 1 ,114691  ,553,553,553
BEGIN DESCRIPTION:
Johnson Creek 157.0
END DESCRIPTION:
XS GIS Cut Line= 3
      1826575.01     13981274.98        1826775.       13980925.
      1827425.01     13979324.98
#Sta/Elev= 30
  4597.5    2112  4655.1 2105.42  4765.7 2098.21  4785.8 2096.94  4890.4 2088.98
    4912 2085.99  4915.3 2084.22  4949.5 2070.92  4955.2 2072.14  4971.1 2068.42
  4977.6 2057.63  4987.5  2055.1    4988  2054.6  5007.9  2055.1  5009.9  2056.8
    5101 2062.03  5146.5  2063.8  5331.2 2062.52    5400 2065.51  5540.1 2065.85
  5593.6 2062.73  5623.1 2063.66  5628.5 2065.68  5652.6 2066.71  5723.8 2068.04
  5920.3 2066.89  6004.4 2068.25  6134.5 2082.52    6652 2103.21  6727.6 2111.16
#Mann= 7 ,-1 , 0
  4597.5     .07       0  4765.7    .035       0  4785.8     .07       0
  4915.3     .07       0  4987.5     .05       0  5007.9     .07       0
    5101     .07       0
Bank Sta=4987.5,5007.9
XS Rating Curve= 0 ,0
Exp/Cntr=0.3,0.1

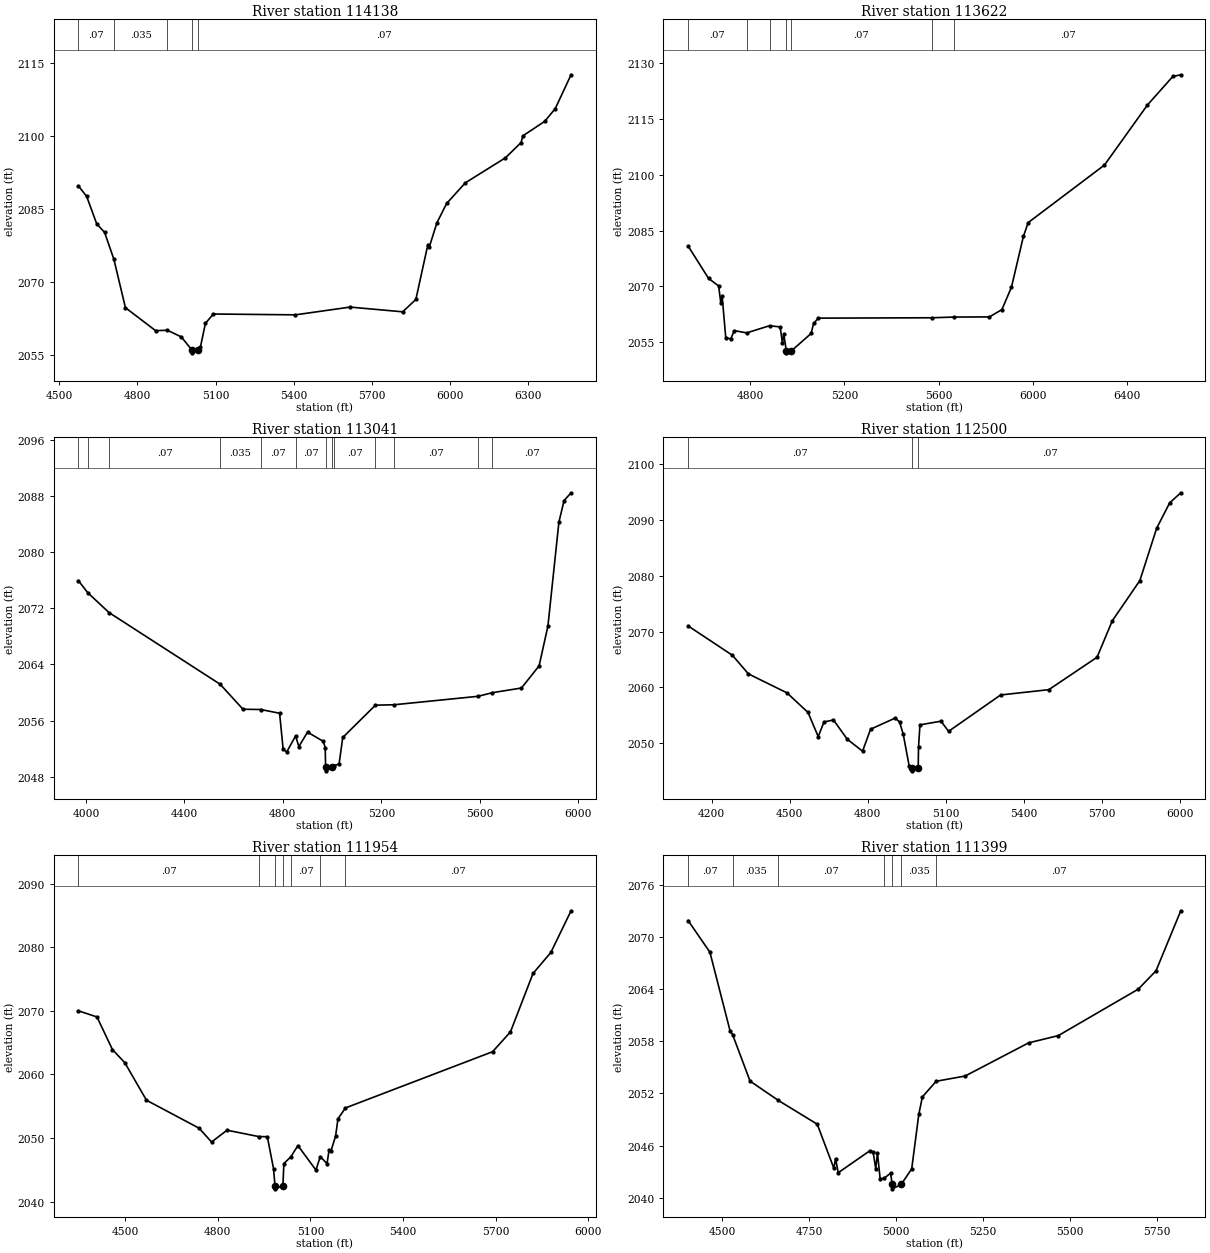
Type RM Length L Ch R = 1 ,114138  ,516,516,516
BEGIN DESCRIPTION:
Johnson Creek 156.0
END DESCRIPTION:
XS GIS Cut Line= 3
      1827125.01     13981174.97        1827275.       13980775.
        1827475.       13979325.
#Sta/Elev= 30
  4573.2 2089.76  4605.2 2087.59  4643.5 2081.99  4673.7 2080.24  4709.4 2074.74
  4753.8 2064.79  4869.5 2060.08    4915 2060.16  4968.3  2058.8  5010.1 2056.03
  5010.6 2055.53  5031.1 2056.03  5041.4 2056.67  5060.9 2061.58  5091.2 2063.49
    5406 2063.32  5616.1 2064.91    5818 2063.94  5868.5 2066.48  5914.6 2077.73
  5919.6 2077.17  5949.3 2082.19  5986.5 2086.15  6058.4 2090.39  6212.4 2095.52
  6272.3 2098.64  6279.2 2100.02  6363.2    2103  6403.5 2105.61  6464.1 2112.54
#Mann= 5 ,-1 , 0
  4573.2     .07       0  4709.4    .035       0    4915     .07       0
  5010.1     .05       0  5031.1     .07       0
Bank Sta=5010.1,5031.1
XS Rating Curve= 0 ,0
Exp/Cntr=0.3,0.1

Type RM Length L Ch R = 1 ,113622  ,581,581,581
BEGIN DESCRIPTION:
Johnson Creek 155.0
END DESCRIPTION:
XS GIS Cut Line= 3
      1827474.99     13981125.02        1827725.       13980725.
      1827475.01     13979125.04
#Sta/Elev= 30
  4536.6 2080.88  4623.3 2072.19  4666.3 2070.13  4675.2 2065.69  4681.1 2067.42
  4696.4 2056.27  4717.6 2055.92    4733 2058.15  4785.2 2057.54  4882.2 2059.46
  4927.5 2059.14    4937 2054.82  4942.9 2057.14  4953.6 2052.68  4954.1 2052.18
  4974.6 2052.68  5058.9 2057.39  5069.1 2060.07  5089.3  2061.5  5569.7  2061.6
  5665.8 2061.79  5815.5 2061.83  5868.6  2063.8  5909.1 2069.82  5959.7 2083.45
    5980 2087.16  6303.9 2102.63    6486 2118.74  6593.8 2126.41  6627.7 2126.87
#Mann= 7 ,-1 , 0
  4536.6     .07       0  4785.2    .035       0  4882.2     .07       0
  4953.6     .05       0  4974.6     .07       0  5569.7    .035       0
  5665.8     .07       0
Bank Sta=4953.6,4974.6
XS Rating Curve= 0 ,0
Exp/Cntr=0.3,0.1

Type RM Length L Ch R = 1 ,113041  ,541,541,541
BEGIN DESCRIPTION:
Johnson Creek 154.0
END DESCRIPTION:
XS GIS Cut Line= 3
      1828875.01     13981325.02        1828225.       13980525.
      1827675.01     13979725.02
#Sta/Elev= 30
  3969.2 2075.92  4007.7 2074.19  4093.5 2071.38  4545.2 2061.17    4638 2057.61
  4710.3 2057.57  4786.7 2057.04    4801 2051.98  4815.4 2051.51  4851.7 2053.81
    4865 2052.29  4900.1 2054.35  4964.1 2053.04    4972 2052.15  4973.7 2049.34
  4974.2 2048.84  4999.1 2049.34  5006.8 2049.58  5028.4 2049.81  5043.3 2053.59
  5176.1 2058.19  5252.1 2058.25  5592.6 2059.45  5651.4 2059.97  5769.2 2060.63
  5840.9 2063.78  5876.8 2069.45  5921.5 2084.27  5942.4 2087.32  5970.8 2088.43
#Mann= 13 ,-1 , 0
  3969.2     .07       0  4007.7      .1       0  4093.5     .07       0
  4545.2    .035       0  4710.3     .07       0  4851.7     .07       0
  4973.7     .05       0  4999.1     .07       0  5006.8     .07       0
  5176.1    .035       0  5252.1     .07       0  5592.6    .035       0
  5651.4     .07       0
Bank Sta=4973.7,4999.1
XS Rating Curve= 0 ,0
Exp/Cntr=0.3,0.1

Type RM Length L Ch R = 1 ,112500  ,546,546,546
BEGIN DESCRIPTION:
Johnson Creek 153.0
END DESCRIPTION:
XS GIS Cut Line= 3
      1829074.99     13981074.99        1828675.       13980275.
      1828075.01     13979475.01
#Sta/Elev= 30
  4109.9 2071.03  4280.4 2065.75  4341.9 2062.41    4490 2059.01  4571.1 2055.49
  4610.2 2051.16  4632.6 2053.79  4668.9 2054.14    4722 2050.68  4780.7 2048.53
  4811.5 2052.48  4906.5 2054.49  4923.3 2053.75  4937.2 2051.57  4959.6 2045.96
  4969.3 2045.51  4969.8 2045.01  4994.7 2045.51  4995.9 2049.28  5001.5 2053.27
  5082.4 2053.92  5111.6  2052.1  5311.6 2058.63    5497 2059.58  5682.4  2065.4
  5740.8 2071.93    5847 2079.17  5911.6 2088.56  5961.6 2093.11  6004.3 2094.92
#Mann= 3 ,-1 , 0
  4109.9     .07       0  4969.3     .05       0  4994.7     .07       0
Bank Sta=4969.3,4994.7
XS Rating Curve= 0 ,0
Exp/Cntr=0.3,0.1

Type RM Length L Ch R = 1 ,111954  ,555,555,555
BEGIN DESCRIPTION:
Johnson Creek 152.0
END DESCRIPTION:
XS GIS Cut Line= 3
        1829225.       13980975.        1829175.       13980325.
      1829674.99     13979525.01
#Sta/Elev= 30
  4348.4 2069.99  4408.6 2069.03  4458.7  2063.9  4498.8 2061.83    4569 2055.93
  4739.5 2051.53  4779.7 2049.36  4829.8 2051.22  4932.2 2050.22  4960.2  2050.2
  4980.3 2045.18    4985  2042.5  4985.5    2042  5010.6  2042.5  5013.9 2045.98
  5036.3 2047.03  5059.3  2048.8  5117.7 2044.95  5131.6 2047.07  5153.6 2045.96
  5160.1 2048.08    5166  2047.9  5181.3  2050.3    5189 2053.01  5213.2 2054.72
  5689.6 2063.56  5747.4 2066.67  5820.5 2075.86  5878.3 2079.17  5943.7 2085.72
#Mann= 7 ,-1 , 0
  4348.4     .07       0  4932.2    .035       0    4985    .035       0
  5010.6    .035       0  5036.3     .07       0  5131.6    .035       0
  5213.2     .07       0
Bank Sta=4985,5010.6
XS Rating Curve= 0 ,0
Exp/Cntr=0.3,0.1

Type RM Length L Ch R = 1 ,111399  ,518,518,518
BEGIN DESCRIPTION:
Johnson Creek 151.0
END DESCRIPTION:
XS GIS Cut Line= 3
        1829725.     13981074.95        1829675.       13980475.
        1829825.     13979674.97
#Sta/Elev= 30
  4402.8 2071.88  4465.5 2068.24  4523.2 2059.23  4531.1 2058.72  4580.9 2053.42
  4662.4 2051.19    4774 2048.46  4821.7  2043.4  4826.7 2044.51  4834.2 2042.88
  4924.6 2045.39  4934.6 2045.25  4942.1 2043.36  4947.1 2045.15  4954.7 2042.19
  4965.1 2042.22  4984.8 2042.82  4989.5 2041.53    4990 2041.03  5015.2 2041.53
  5045.5 2043.33  5065.9  2049.6  5076.1  2051.6  5115.8  2053.4    5199    2054
  5381.3 2057.81  5466.9 2058.65  5696.7 2063.99  5747.6  2066.1  5818.8    2073
#Mann= 7 ,-1 , 0
  4402.8     .07       0  4531.1    .035       0  4662.4     .07       0
  4965.1    .035       0  4989.5    .035       0  5015.2    .035       0
  5115.8     .07       0
Bank Sta=4989.5,5015.2
XS Rating Curve= 0 ,0
Exp/Cntr=0.3,0.1

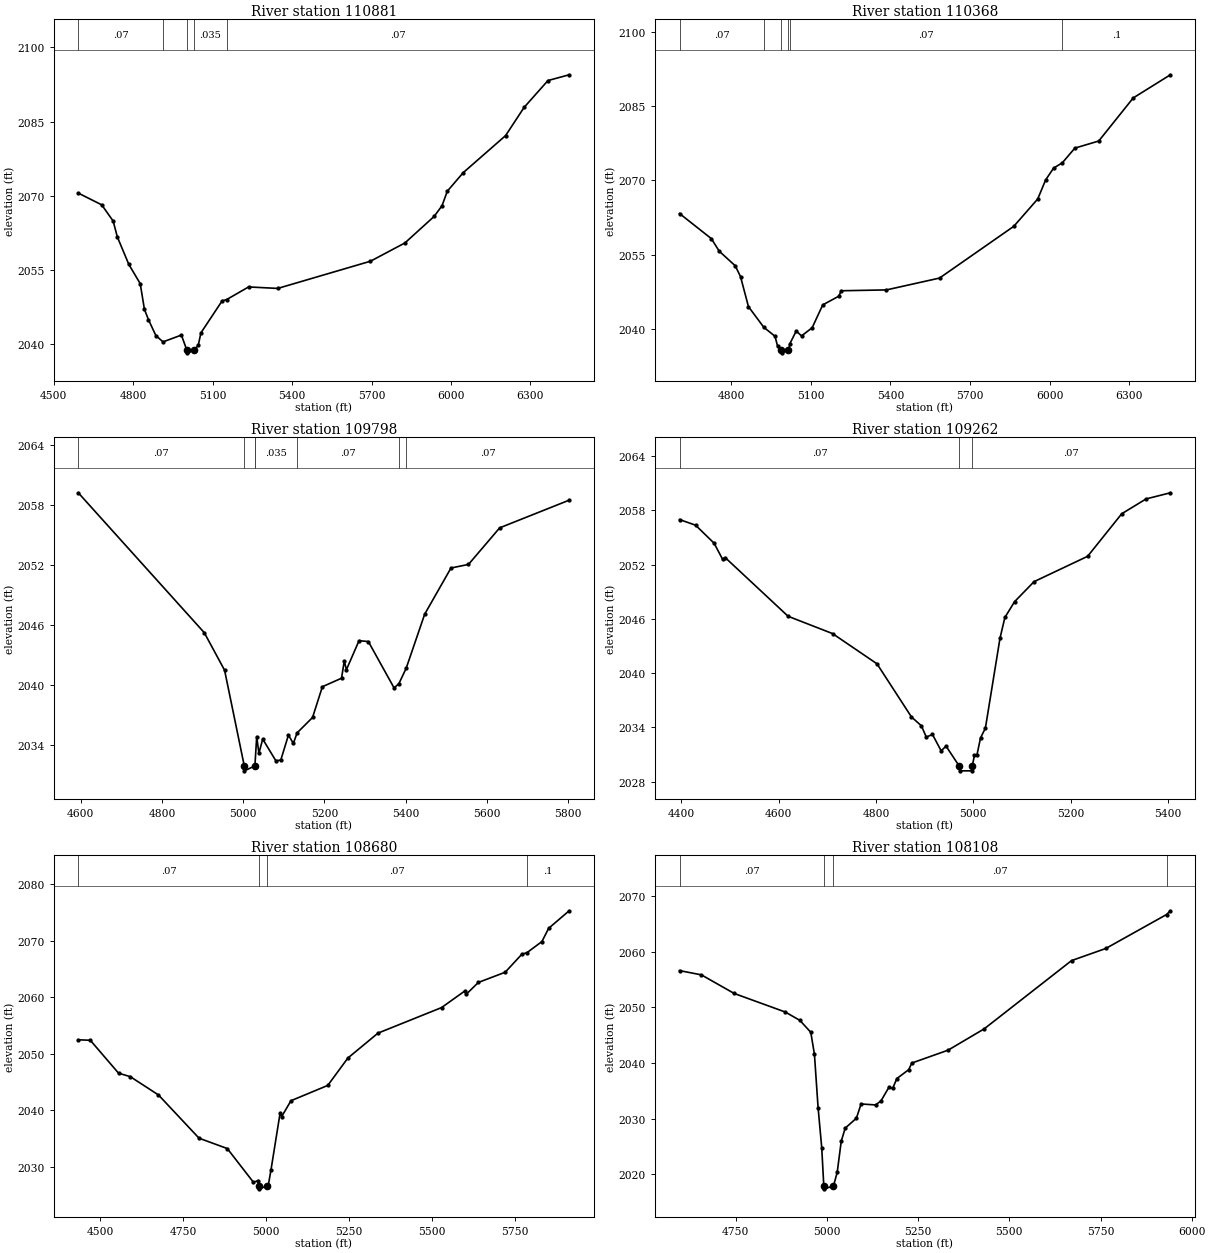
Type RM Length L Ch R = 1 ,110881  ,513,513,513
BEGIN DESCRIPTION:
Johnson Creek 150.0
END DESCRIPTION:
XS GIS Cut Line= 3
      1829874.99     13981125.02        1830075.       13980775.
        1830125.     13979324.99
#Sta/Elev= 30
  4592.2  2070.5  4680.8 2068.12    4724 2064.83  4739.8 2061.61    4783 2056.07
  4826.2 2052.15    4842 2046.96  4857.1 2044.88  4885.2 2041.64  4912.3 2040.36
  4981.7 2041.74  5002.5 2038.64    5003 2038.14  5028.2 2038.64  5045.4 2039.67
  5055.4 2042.19  5135.4 2048.66  5152.8 2048.94  5235.5 2051.49  5345.5 2051.19
  5695.7  2056.7  5825.8  2060.4  5935.9 2065.76  5965.9 2067.93  5985.9 2070.88
    6046 2074.64  6206.1 2082.15  6276.1 2087.87  6366.1  2093.3  6446.2 2094.47
#Mann= 5 ,-1 , 0
  4592.2     .07       0  4912.3    .035       0  5002.5    .035       0
  5028.2    .035       0  5152.8     .07       0
Bank Sta=5002.5,5028.2
XS Rating Curve= 0 ,0
Exp/Cntr=0.3,0.1

Type RM Length L Ch R = 1 ,110368  ,570,570,570
BEGIN DESCRIPTION:
Johnson Creek 149.0
END DESCRIPTION:
XS GIS Cut Line= 3
        1830525.     13981275.02        1830525.       13980875.
        1830575.     13979424.99
#Sta/Elev= 30
  4604.6 2063.31  4724.6 2058.24  4754.6 2055.69  4814.6 2052.77  4834.6 2050.58
  4864.6 2044.51  4922.5 2040.34  4964.6 2038.54  4974.6 2036.49  4989.1 2035.69
  4989.6 2035.19  5015.2 2035.69  5020.8 2037.04  5044.6 2039.59  5064.7 2038.61
  5104.7 2040.25  5144.7 2044.87  5204.7 2046.61  5214.7 2047.72  5384.8 2047.89
    5585 2050.28  5865.1 2060.73  5955.2 2066.24  5985.2  2070.1  6015.2 2072.48
  6047.9 2073.54  6095.3 2076.51  6185.3 2077.94  6315.4 2086.64  6455.5 2091.31
#Mann= 6 ,-1 , 0
  4604.6     .07       0  4922.5    .035       0  4989.1    .035       0
  5015.2    .035       0  5020.8     .07       0  6047.9      .1       0
Bank Sta=4989.1,5015.2
XS Rating Curve= 0 ,0
Exp/Cntr=0.3,0.1

Type RM Length L Ch R = 1 ,109798  ,536,536,536
BEGIN DESCRIPTION:
Johnson Creek 148.0
END DESCRIPTION:
XS GIS Cut Line= 3
        1831075.     13981224.99        1831075.       13980825.
      1831375.01     13980074.97
#Sta/Elev= 30
  4594.2 2059.21  4904.2 2045.21  4954.2 2041.45  5002.6 2031.88  5003.1 2031.38
  5028.8 2031.88    5029 2032.01  5033.2  2034.8  5038.6 2033.14    5048 2034.56
  5080.4 2032.38  5092.5 2032.46  5111.3 2034.96  5123.4 2034.12  5132.6 2035.18
  5170.6 2036.72  5194.8  2039.8  5241.9 2040.65  5248.6 2042.35    5254 2041.51
    5285 2044.41  5307.9 2044.32  5371.2 2039.68    5383  2040.1  5401.1 2041.66
  5446.5 2047.06  5511.2 2051.68  5554.3 2052.04    5631  2055.7    5802 2058.47
#Mann= 7 ,-1 , 0
  4594.2     .07       0  5002.6     .05       0  5028.8     .07       0
    5029    .035       0  5132.6     .07       0    5383    .035       0
  5401.1     .07       0
Bank Sta=5002.6,5028.8
XS Rating Curve= 0 ,0
Exp/Cntr=0.3,0.1

Type RM Length L Ch R = 1 ,109262  ,582,582,582
BEGIN DESCRIPTION:
Johnson Creek 147.0
END DESCRIPTION:
XS GIS Cut Line= 3
      1831424.99     13981175.04        1831525.       13980575.
        1831525.     13980175.02
#Sta/Elev= 30
  4396.4 2056.98  4429.4 2056.36  4467.4 2054.37  4485.1 2052.57  4490.2 2052.78
  4619.5 2046.29  4710.7 2044.38    4802 2041.04  4872.9 2035.16  4893.2 2034.19
  4903.3 2032.94    4916 2033.23  4933.8 2031.42  4943.9 2031.94  4971.3 2029.71
  4971.8 2029.21  4997.1 2029.21  4997.6 2029.71  5002.2 2030.93  5007.2 2030.93
  5014.7 2032.85  5024.7 2033.93  5054.7 2043.87  5064.7 2046.16  5084.7 2047.91
  5124.7 2050.12  5234.7 2052.92  5304.7 2057.62  5354.7 2059.26  5404.7 2059.94
#Mann= 3 ,-1 , 0
  4396.4     .07       0  4971.3     .05       0  4997.6     .07       0
Bank Sta=4971.3,4997.6
XS Rating Curve= 0 ,0
Exp/Cntr=0.3,0.1

Type RM Length L Ch R = 1 ,108680  ,572,572,572
BEGIN DESCRIPTION:
Johnson Creek 146.0
END DESCRIPTION:
XS GIS Cut Line= 3
        1831725.       13981125.        1832075.       13980675.
      1831961.19     13979773.65
#Sta/Elev= 30
  4433.7 2052.44  4469.9 2052.36    4555 2046.54  4590.3 2045.92  4675.3 2042.68
  4797.5 2035.03  4882.5  2033.2  4961.3 2027.23  4975.7 2027.54  4977.1 2026.57
  4977.6 2026.07  5003.4 2026.57  5006.3  2026.8  5013.9 2029.32  5041.4 2039.41
  5046.4 2038.86  5074.3 2041.66  5185.2 2044.37  5245.7 2049.21  5336.4 2053.62
  5527.9 2058.14    5598 2061.08    5603 2060.54  5638.8 2062.59  5719.4 2064.39
  5769.8 2067.58  5785.3 2067.86  5830.3 2069.83  5850.5 2072.17  5912.3 2075.27
#Mann= 4 ,-1 , 0
  4433.7     .07       0  4977.1     .05       0  5003.4     .07       0
  5785.3      .1       0
Bank Sta=4977.1,5003.4
XS Rating Curve= 0 ,0
Exp/Cntr=0.3,0.1

Type RM Length L Ch R = 1 ,108108  ,585,585,585
BEGIN DESCRIPTION:
Johnson Creek 145.0
END DESCRIPTION:
XS GIS Cut Line= 3
        1832575.     13981074.96        1832575.       13980675.
      1832200.33      13979806.1
#Sta/Elev= 30
  4595.5 2056.64  4655.5 2055.87  4745.5 2052.52  4885.5 2049.18  4925.5 2047.68
  4955.5 2045.53  4965.5 2041.58  4975.5 2031.98  4985.5 2024.78  4991.2 2017.84
  4991.7 2017.34  5017.7 2017.84    5028 2020.32    5039 2025.91  5049.9 2028.27
  5080.5 2030.05  5093.5 2032.62    5133 2032.45  5147.9 2033.16  5169.7 2035.62
    5180 2035.41  5191.5  2037.2  5224.2 2038.81  5232.5 2039.99    5332 2042.31
  5431.1 2046.15  5670.6 2058.44  5764.5 2060.62    5931 2066.73  5941.7 2067.41
#Mann= 4 ,-1 , 0
  4595.5     .07       0  4991.2     .05       0  5017.7     .07       0
    5931      .1       0
Bank Sta=4991.2,5017.7
XS Rating Curve= 0 ,0
Exp/Cntr=0.3,0.1

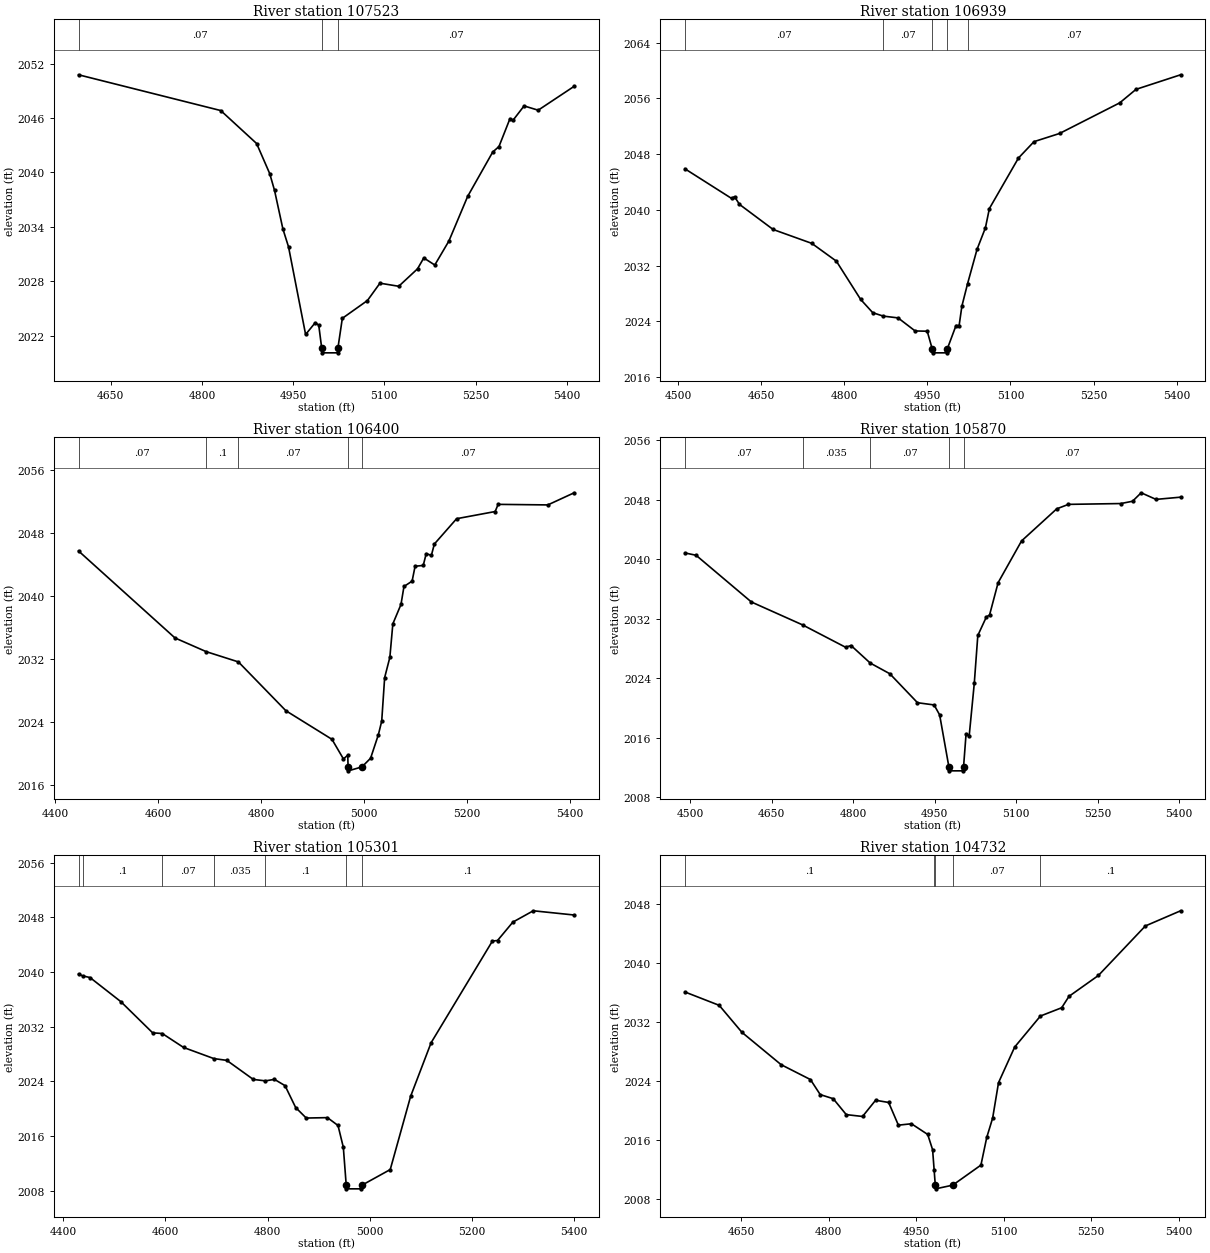
Type RM Length L Ch R = 1 ,107523  ,584,584,584
BEGIN DESCRIPTION:
Johnson Creek 144.0
END DESCRIPTION:
XS GIS Cut Line= 3
        1833175.       13980625.        1832975.       13980275.
      1832875.01     13979875.03
#Sta/Elev= 30
  4596.9 2050.76  4830.9 2046.82  4889.9 2043.19  4911.5 2039.87  4919.4 2038.02
  4933.1 2033.79  4942.4 2031.81  4970.5 2022.16  4986.3 2023.46  4992.1 2023.19
    4997 2020.64  4997.5 2020.14  5023.1 2020.14  5023.6 2020.64  5030.9 2023.94
  5072.2  2025.9  5092.8 2027.81  5123.7 2027.47  5154.6 2029.39  5164.9 2030.59
    5183 2029.81  5206.2 2032.45  5237.1 2037.37  5278.3 2042.25  5288.6 2042.86
  5306.7 2045.93  5311.8 2045.76  5329.9 2047.33  5353.1 2046.86  5412.3 2049.49
#Mann= 3 ,-1 , 0
  4596.9     .07       0    4997     .05       0  5023.6     .07       0
Bank Sta=4997,5023.6
XS Rating Curve= 0 ,0
Exp/Cntr=0.3,0.1

Type RM Length L Ch R = 1 ,106939  ,539,539,539
BEGIN DESCRIPTION:
Johnson Creek 143.0
END DESCRIPTION:
XS GIS Cut Line= 3
      1833524.99     13980274.97        1833325.       13979825.
      1833125.01     13979475.02
#Sta/Elev= 30
  4511.9 2045.89    4596 2041.65  4601.5 2041.89  4610.4 2040.79  4671.2 2037.19
    4741  2035.2  4785.4 2032.65  4829.2 2027.17  4851.1 2025.26    4870 2024.77
  4896.9 2024.51  4927.7 2022.64  4949.6  2022.6  4958.8    2020  4959.3  2019.5
    4985  2019.5  4985.5    2020  5001.6 2023.42  5007.2 2023.42  5012.2  2026.2
  5022.5 2029.43  5039.6 2034.35  5054.7 2037.43  5061.9  2040.2  5114.4 2047.44
  5142.5 2049.79  5188.6 2050.96  5297.3 2055.35  5326.8 2057.29  5407.4 2059.38
#Mann= 5 ,-1 , 0
  4511.9     .07       0    4870     .07       0  4958.8     .05       0
  4985.5     .07       0  5022.5     .07       0
Bank Sta=4958.8,4985.5
XS Rating Curve= 0 ,0
Exp/Cntr=0.3,0.1

Type RM Length L Ch R = 1 ,106400  ,530,530,530
BEGIN DESCRIPTION:
Johnson Creek 142.0
END DESCRIPTION:
XS GIS Cut Line= 3
      1834025.02     13980075.04        1833775.       13979575.
      1833424.98     13979374.99
#Sta/Elev= 30
  4445.5 2045.67  4632.8 2034.63  4693.5 2032.89  4755.9 2031.59    4848  2025.4
  4937.5 2021.77  4959.8 2019.28  4968.2 2019.75  4968.8 2018.27  4969.3 2017.77
  4995.7 2018.27  5012.5 2019.37  5027.6 2022.35  5034.1 2024.08  5039.8  2029.6
  5049.9 2032.17  5055.7 2036.42  5071.5 2038.88  5077.3 2041.16  5093.1 2041.84
  5098.9 2043.73  5114.7 2043.83  5120.5 2045.33  5130.5 2045.11  5136.3 2046.55
  5179.5 2049.76  5254.3 2050.67  5260.1 2051.58  5356.6 2051.51  5407.7 2053.05
#Mann= 5 ,-1 , 0
  4445.5     .07       0  4693.5      .1       0  4755.9     .07       0
  4968.8     .05       0  4995.7     .07       0
Bank Sta=4968.8,4995.7
XS Rating Curve= 0 ,0
Exp/Cntr=0.3,0.1

Type RM Length L Ch R = 1 ,105870  ,569,569,569
BEGIN DESCRIPTION:
Johnson Creek 141.0
END DESCRIPTION:
XS GIS Cut Line= 3
      1834374.99     13979974.96        1834275.       13979475.
      1834074.99     13979124.98
#Sta/Elev= 30
  4490.1 2040.86  4510.5 2040.55  4612.4 2034.26  4706.6 2031.18  4785.8 2028.17
    4796  2028.4  4831.3 2026.04  4867.4  2024.6  4918.4  2020.7    4949  2020.4
  4959.2 2019.06  4976.3 2012.03  4976.8 2011.53  5002.7 2011.53  5003.2 2012.03
  5007.9 2016.53  5013.6 2016.23    5023 2023.31  5029.5 2029.75  5045.3 2032.25
  5051.1  2032.5  5066.9 2036.86  5110.1 2042.48  5174.9  2046.8  5196.5  2047.4
  5292.9 2047.51  5314.5 2047.82  5330.4 2048.96  5357.7 2048.07  5403.1 2048.37
#Mann= 5 ,-1 , 0
  4490.1     .07       0  4706.6    .035       0  4831.3     .07       0
  4976.3     .05       0  5003.2     .07       0
Bank Sta=4976.3,5003.2
XS Rating Curve= 0 ,0
Exp/Cntr=0.3,0.1

Type RM Length L Ch R = 1 ,105301  ,569,569,569
BEGIN DESCRIPTION:
Johnson Creek 140.0
END DESCRIPTION:
XS GIS Cut Line= 3
        1834675.       13979975.        1834825.       13979425.
        1834825.     13979024.99
#Sta/Elev= 30
  4429.8 2039.73  4437.7 2039.46  4452.3 2039.21  4512.7 2035.68  4574.9 2031.12
  4593.7 2031.02  4635.4 2028.98  4694.7 2027.35    4720 2027.09  4771.9  2024.3
  4795.7 2024.09  4813.3 2024.31    4834 2023.39  4854.8 2020.19  4875.5 2018.65
    4917 2018.71  4937.7 2017.56  4948.1 2014.37  4953.8 2008.79  4954.3 2008.29
  4983.2 2008.29  4983.7 2008.79  5039.9 2011.11  5079.9 2021.85  5119.9 2029.67
  5239.9 2044.55  5249.9 2044.63  5279.9 2047.32  5319.9 2048.98  5399.9 2048.36
#Mann= 7 ,-1 , 0
  4429.8     .07       0  4437.7      .1       0  4593.7     .07       0
  4694.7    .035       0  4795.7      .1       0  4953.8     .05       0
  4983.7      .1       0
Bank Sta=4953.8,4983.7
XS Rating Curve= 0 ,0
Exp/Cntr=0.3,0.1

Type RM Length L Ch R = 1 ,104732  ,535,535,535
BEGIN DESCRIPTION:
Johnson Creek 139.0
END DESCRIPTION:
XS GIS Cut Line= 3
      1835125.01     13980024.98        1835325.       13979625.
        1835375.       13979225.
#Sta/Elev= 30
  4553.2 2036.07  4611.9 2034.26    4651 2030.59  4718.1 2026.21  4768.4 2024.19
  4785.2 2022.15  4807.5 2021.59  4829.9 2019.43  4857.8 2019.18  4880.2 2021.38
  4902.6 2021.08  4919.3    2018  4941.7 2018.19  4969.6 2016.74    4978 2014.67
  4980.7 2011.85  4982.6 2009.86  4983.1 2009.36  5012.5 2009.86  5060.9 2012.58
  5070.9 2016.34    5081 2018.96  5091.1 2023.77  5118.8  2028.6    5163 2032.81
  5199.4 2033.93    5212 2035.48  5262.4 2038.31    5343 2045.03  5403.5 2047.09
#Mann= 5 ,-1 , 0
  4553.2      .1       0  4980.7     .07       0  4982.6     .05       0
  5012.5     .07       0    5163      .1       0
Bank Sta=4982.6,5012.5
XS Rating Curve= 0 ,0
Exp/Cntr=0.3,0.1

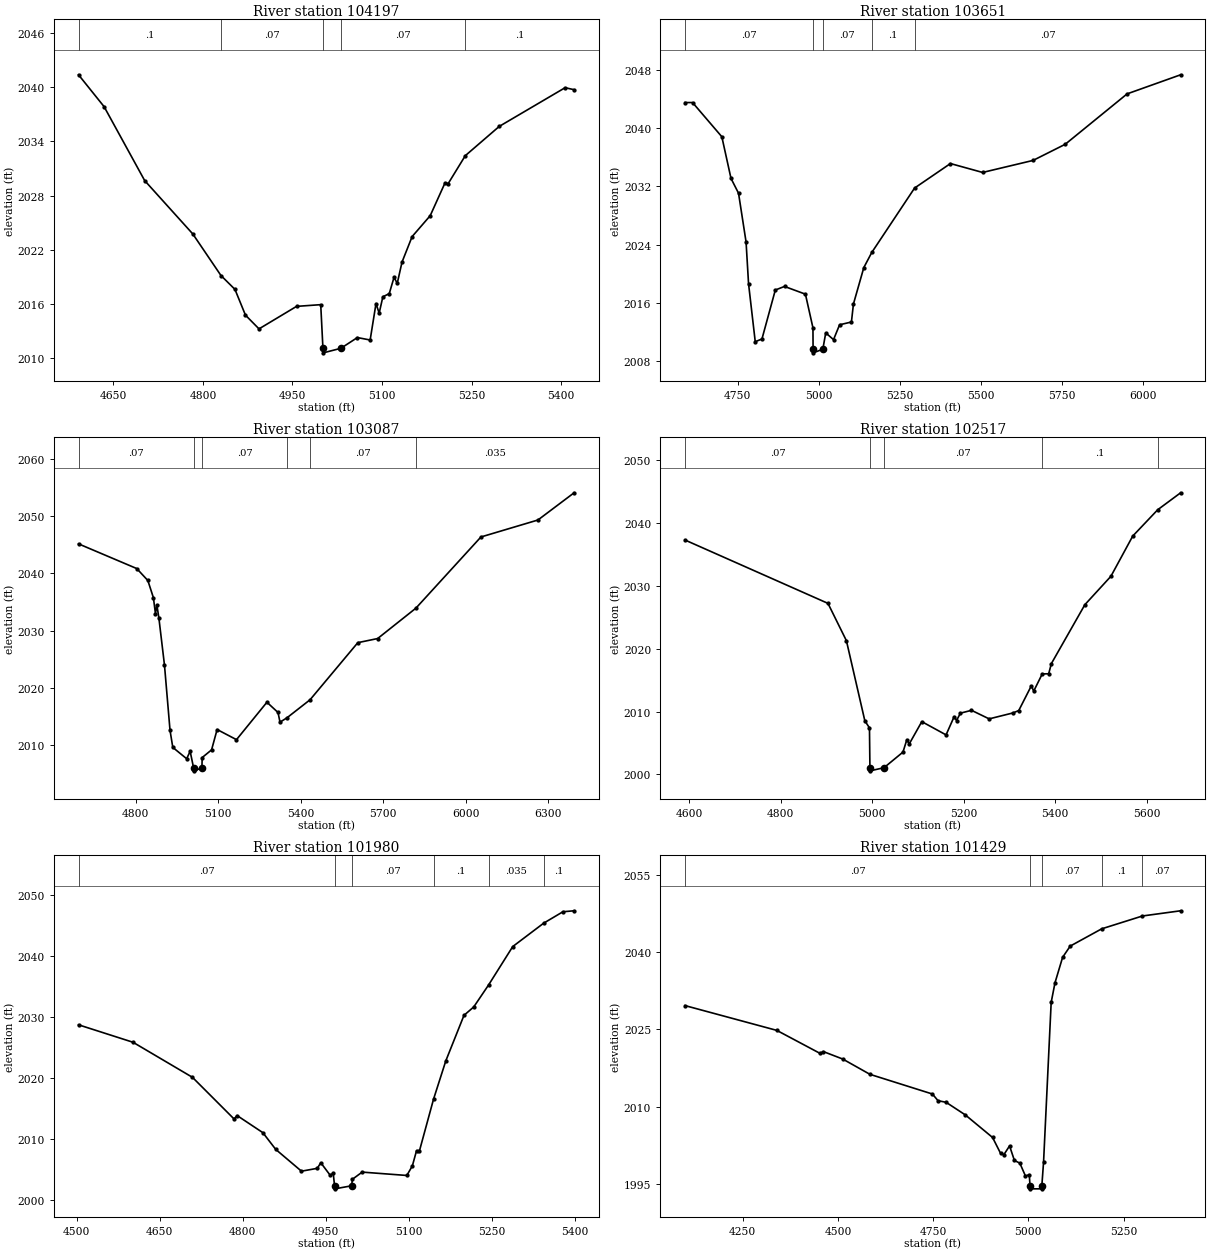
Type RM Length L Ch R = 1 ,104197  ,546,546,546
BEGIN DESCRIPTION:
Johnson Creek 138.0
END DESCRIPTION:
XS GIS Cut Line= 3
        1835725.     13980175.03        1835775.       13979775.
      1835625.01     13979375.04
#Sta/Elev= 30
  4591.6 2041.36  4634.5 2037.83  4702.5 2029.65  4783.1 2023.75  4830.3 2019.15
  4853.7 2017.62  4871.3 2014.77    4894 2013.25  4956.9 2015.74  4997.4 2015.93
  5001.1  2011.1  5001.6  2010.6  5031.1  2011.1  5058.8 2012.29  5080.2 2012.02
    5090 2016.05  5095.3 2014.99  5101.5  2016.8  5112.2 2017.15  5120.2 2018.95
  5125.6 2018.29  5133.6 2020.64  5150.5 2023.46  5180.8 2025.77  5205.7 2029.41
    5211 2029.33  5239.6 2032.41  5296.5 2035.65  5406.8 2039.93  5421.9 2039.71
#Mann= 5 ,-1 , 0
  4591.6      .1       0  4830.3     .07       0  5001.1     .05       0
  5031.1     .07       0  5239.6      .1       0
Bank Sta=5001.1,5031.1
XS Rating Curve= 0 ,0
Exp/Cntr=0.3,0.1

Type RM Length L Ch R = 1 ,103651  ,564,564,564
BEGIN DESCRIPTION:
Johnson Creek 137.0
END DESCRIPTION:
XS GIS Cut Line= 4
        1836375.     13980224.98        1836275.       13979825.
        1836125.       13979425.      1835638.65     13978938.07
#Sta/Elev= 30
  4588.1  2043.5  4611.3  2043.5  4701.5 2038.81  4729.8 2033.09    4753 2031.06
  4776.2 2024.38  4783.9 2018.63  4804.5 2010.69  4825.2 2011.06  4866.4 2017.78
  4894.7 2018.27  4959.2 2017.21  4982.4 2012.59  4982.8 2009.66  4983.3 2009.16
  5012.9 2009.66  5021.8  2011.9  5045.8 2010.97  5064.5 2013.01    5101 2013.39
  5107.2 2015.86  5139.2 2020.86  5163.7 2022.93  5295.7 2031.77  5406.2 2035.13
  5505.4 2033.91  5660.9 2035.56  5759.9 2037.77  5950.8 2044.69  6115.8 2047.31
#Mann= 5 ,-1 , 0
  4588.1     .07       0  4982.8     .05       0  5012.9     .07       0
  5163.7      .1       0  5295.7     .07       0
Bank Sta=4982.8,5012.9
XS Rating Curve= 0 ,0
Exp/Cntr=0.3,0.1

Type RM Length L Ch R = 1 ,103087  ,570,570,570
BEGIN DESCRIPTION:
Johnson Creek 136.0
END DESCRIPTION:
XS GIS Cut Line= 4
      1836725.01     13980224.96        1836775.       13979825.
      1836674.59     13978880.23      1836557.99     13978448.15
#Sta/Elev= 30
  4592.4 2045.17    4804 2040.86  4844.3 2038.78  4864.5 2035.78    4872 2032.99
  4877.1 2034.51  4884.6 2032.17  4904.8    2024  4924.9 2012.64    4935 2009.66
  4985.4 2007.68    4998 2008.98  5010.6 2006.07  5011.1 2005.57  5040.7 2006.07
  5041.8 2007.89  5075.9 2009.23    5096 2012.78  5166.4 2011.01    5277 2017.54
  5317.3 2015.75  5324.5 2014.06    5350 2014.83  5433.7 2017.97  5607.2 2027.93
  5679.3 2028.65  5818.3 2033.95  6054.6 2046.37  6261.7 2049.33  6393.1 2054.08
#Mann= 6 ,-1 , 0
  4592.4     .07       0  5010.6     .05       0  5040.7     .07       0
    5350      .1       0  5433.7     .07       0  5818.3    .035       0
Bank Sta=5010.6,5040.7
XS Rating Curve= 0 ,0
Exp/Cntr=0.3,0.1

Type RM Length L Ch R = 1 ,102517  ,537,537,537
BEGIN DESCRIPTION:
Johnson Creek 135.0
END DESCRIPTION:
XS GIS Cut Line= 3
        1837225.     13980024.99        1837275.       13979625.
      1837475.01     13978974.98
#Sta/Elev= 30
  4591.2  2037.3  4903.6 2027.22  4943.9 2021.28  4984.2 2008.53  4994.3 2007.41
  4995.3 2001.07  4995.8 2000.57  5026.1 2001.07  5067.5 2003.55    5076 2005.53
  5081.3 2004.86  5108.7  2008.4  5161.7 2006.29  5179.4  2009.2  5184.6 2008.58
  5193.1 2009.75  5217.3  2010.2  5255.9 2008.84  5308.2 2009.79  5320.6 2010.17
  5348.1  2014.1  5353.3 2013.26  5371.9 2015.99    5386 2016.02  5391.9 2017.64
  5465.1 2027.01    5522 2031.53  5569.7 2037.93  5624.3 2042.12  5674.4 2044.82
#Mann= 5 ,-1 , 0
  4591.2     .07       0  4995.3     .05       0  5026.1     .07       0
  5371.9      .1       0  5624.3     .07       0
Bank Sta=4995.3,5026.1
XS Rating Curve= 0 ,0
Exp/Cntr=0.3,0.1

Type RM Length L Ch R = 1 ,101980  ,551,551,551
BEGIN DESCRIPTION:
Johnson Creek 134.0
END DESCRIPTION:
XS GIS Cut Line= 3
      1837524.98     13979825.04        1837725.       13979375.
        1837675.     13978974.99
#Sta/Elev= 30
  4503.1  2028.7  4601.6 2025.84    4709  2020.1  4784.2 2013.28  4789.7 2013.84
  4836.2 2011.04  4859.5  2008.3    4906 2004.73  4934.7  2005.2  4940.9 2006.12
    4958 2004.05  4963.4  2004.4  4965.8 2002.34  4966.3 2001.84  4996.6 2002.34
  4998.1 2003.41  5015.7 2004.58  5096.4 2004.03  5106.4  2005.6    5114  2008.1
    5119 2007.99  5144.7 2016.53  5166.9 2022.81  5199.7 2030.25  5217.3 2031.62
  5244.2 2035.23  5287.8 2041.51  5343.7 2045.34  5378.5 2047.21  5398.7 2047.37
#Mann= 6 ,-1 , 0
  4503.1     .07       0  4965.8     .05       0  4996.6     .07       0
  5144.7      .1       0  5244.2    .035       0  5343.7      .1       0
Bank Sta=4965.8,4996.6
XS Rating Curve= 0 ,0
Exp/Cntr=0.3,0.1

Type RM Length L Ch R = 1 ,101429  ,559,559,559
BEGIN DESCRIPTION:
Johnson Creek 133.0
END DESCRIPTION:
XS GIS Cut Line= 3
      1837710.73      13980165.5        1838225.       13979425.
        1838225.     13979024.97
#Sta/Elev= 30
  4098.4 2029.62  4339.5 2024.81    4453 2020.35  4461.7  2020.7  4512.4 2019.26
    4584 2016.29  4748.1 2012.47  4762.9 2011.17  4783.9 2010.87  4834.5 2008.42
  4906.1 2004.04    4927 2000.98  4935.8 2000.71  4950.7 2002.41  4963.4 1999.59
  4977.7 1999.06  4992.5 1996.56  5002.5 1996.84  5004.5 1994.58    5005 1994.08
  5034.9 1994.08  5035.4 1994.58    5040 1999.27    5060 2030.25    5070 2034.04
    5090 2038.98    5110 2041.16  5192.7 2044.51  5299.7    2047    5400 2048.01
#Mann= 5 ,-1 , 0
  4098.4     .07       0  5004.5     .05       0  5035.4     .07       0
  5192.7      .1       0  5299.7     .07       0
Bank Sta=5004.5,5035.4
XS Rating Curve= 0 ,0
Exp/Cntr=0.3,0.1