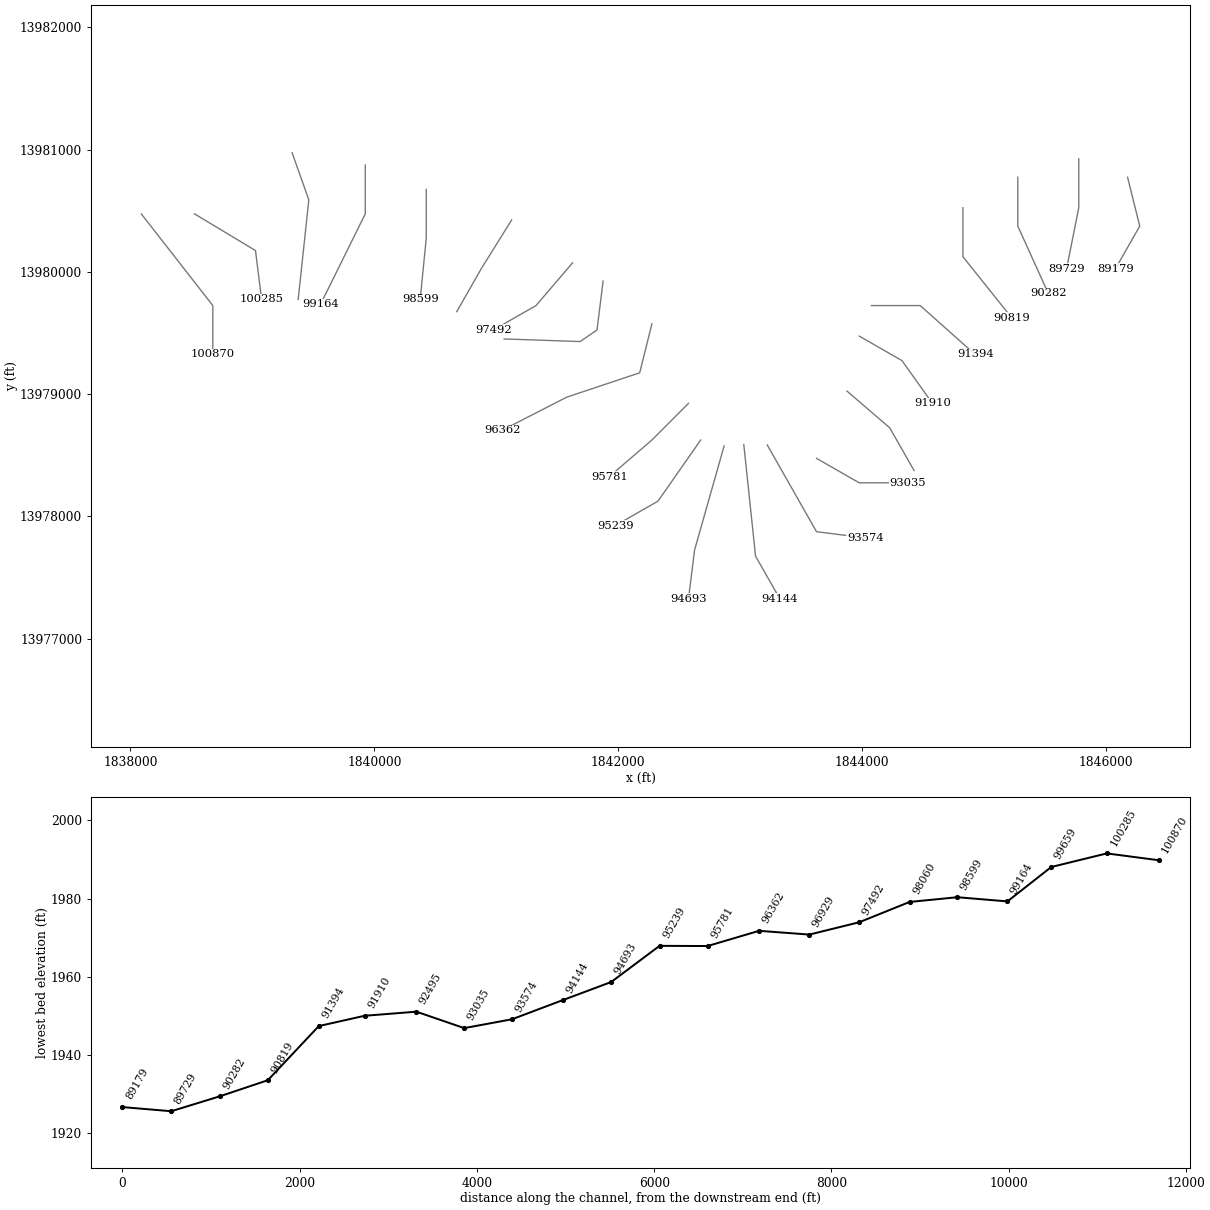
HEC-RAS study Johnson Creek.prj: Johnson Creek Base Level Engineering

--- Johnson Creek.g01 (geometry) --- (continued)

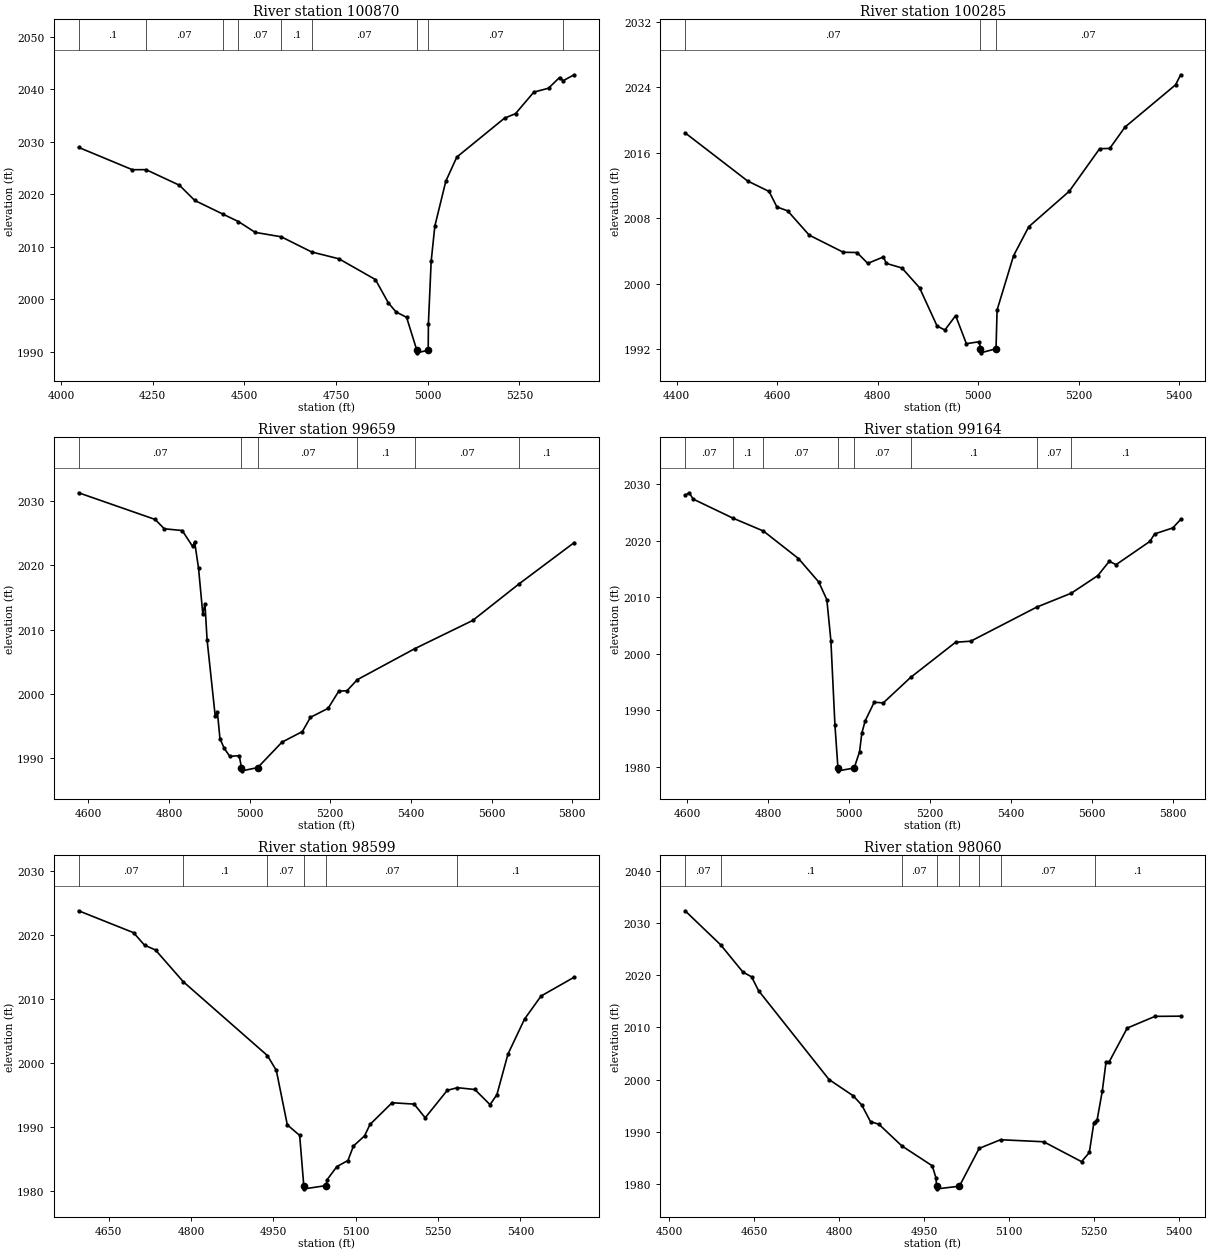
Type RM Length L Ch R = 1 ,100870  ,585,585,585
BEGIN DESCRIPTION:
Johnson Creek 132.0
END DESCRIPTION:
XS GIS Cut Line= 3
      1838088.93     13980474.39        1838675.       13979725.
        1838675.     13979324.95
#Sta/Elev= 30
    4048  2028.9  4194.5 2024.65  4231.8 2024.66  4322.9 2021.69  4364.6  2018.8
  4440.8 2016.22  4483.4 2014.79  4529.6 2012.72  4600.5 2011.88  4683.5 2008.99
  4757.9 2007.69  4857.4 2003.74  4892.6  1999.3  4913.5 1997.58  4942.4 1996.55
  4970.3 1990.29  4970.8 1989.79  5001.3 1990.29  5001.9 1995.37  5009.4 2007.21
  5019.4 2013.91  5049.4 2022.47  5079.4 2027.06  5209.4 2034.46  5239.4 2035.32
  5289.4 2039.42  5329.4 2040.16  5359.4  2042.2  5369.2 2041.59  5399.4 2042.72
#Mann= 9 ,-1 , 0
    4048      .1       0  4231.8     .07       0  4440.8      .1       0
  4483.4     .07       0  4600.5      .1       0  4683.5     .07       0
  4970.3     .05       0  5001.3     .07       0  5369.2      .1       0
Bank Sta=4970.3,5001.3
XS Rating Curve= 0 ,0
Exp/Cntr=0.3,0.1

Type RM Length L Ch R = 1 ,100285  ,626,626,626
BEGIN DESCRIPTION:
Johnson Creek 131.0
END DESCRIPTION:
XS GIS Cut Line= 3
      1838524.99     13980475.01        1839025.       13980175.
        1839075.     13979775.02
#Sta/Elev= 30
  4416.6 2018.44    4541 2012.55  4583.8 2011.27  4599.3 2009.37  4620.7  2008.9
  4663.5 2005.93  4731.5 2003.83  4758.7  2003.8  4780.1 2002.47  4811.2 2003.26
    4817 2002.47  4848.1 2001.91  4883.1  1999.5  4918.1 1994.81  4933.6 1994.32
    4955 1996.08  4976.4 1992.65  5002.2 1992.89  5004.4 1992.03  5004.9 1991.53
  5035.4 1992.03  5037.5 1996.77  5070.3 2003.41  5100.5 2006.95  5181.1 2011.29
  5241.6  2016.5  5261.7 2016.53    5292 2019.14  5392.7 2024.31  5402.8 2025.54
#Mann= 3 ,-1 , 0
  4416.6     .07       0  5004.4     .05       0  5035.4     .07       0
Bank Sta=5004.4,5035.4
XS Rating Curve= 0 ,0
Exp/Cntr=0.3,0.1

Type RM Length L Ch R = 1 ,99659   ,495,495,495
BEGIN DESCRIPTION:
Johnson Creek 130.0
END DESCRIPTION:
XS GIS Cut Line= 3
      1839325.01     13980974.97      1839462.13     13980589.77
        1839375.     13979774.99
#Sta/Elev= 30
  4576.3 2031.29  4766.1 2027.14  4788.6 2025.69    4833 2025.42  4858.6 2022.97
  4863.9 2023.61  4873.5 2019.57  4884.1 2012.43  4889.4 2014.04  4894.7 2008.42
  4914.9 1996.54  4920.2 1997.24  4926.6 1993.07  4937.2 1991.54  4951.1  1990.3
  4974.3 1990.41    4980 1988.55    4981 1988.05  5020.1 1988.55  5080.5 1992.52
  5130.8 1994.15  5150.9 1996.37  5194.7 1997.77  5221.3 2000.46  5241.4  2000.5
  5266.9 2002.22  5409.3 2007.04  5553.2 2011.44  5667.3 2017.09  5804.6 2023.54
#Mann= 6 ,-1 , 0
  4576.3     .07       0    4980     .05       0  5020.1     .07       0
  5266.9      .1       0  5409.3     .07       0  5667.3      .1       0
Bank Sta=4980,5020.1
XS Rating Curve= 0 ,0
Exp/Cntr=0.3,0.1

Type RM Length L Ch R = 1 ,99164   ,565,565,565
BEGIN DESCRIPTION:
Johnson Creek 129.0
END DESCRIPTION:
XS GIS Cut Line= 3
        1839925.     13980874.97        1839925.       13980475.
      1839559.12      13979737.1
#Sta/Elev= 30
  4595.5 2028.02  4605.5 2028.46  4615.5 2027.34  4713.4 2023.98  4788.7  2021.7
  4875.5 2016.82  4925.5 2012.67  4945.5 2009.54  4955.5 2002.29  4965.5 1987.35
  4972.9 1979.76  4973.9 1979.26    5013 1979.76  5026.3 1982.64  5031.9 1985.95
  5040.1 1988.09  5062.4  1991.4  5084.8 1991.28  5152.2 1995.78  5263.4 2002.01
  5300.9  2002.2  5463.5 2008.22  5549.3  2010.7  5614.7 2013.81  5642.9 2016.34
  5659.6 2015.74  5743.3 2019.86  5754.8 2021.18  5799.7 2022.24  5819.1 2023.74
#Mann= 8 ,-1 , 0
  4595.5     .07       0  4713.4      .1       0  4788.7     .07       0
  4972.9     .05       0    5013     .07       0  5152.2      .1       0
  5463.5     .07       0  5549.3      .1       0
Bank Sta=4972.9,5013
XS Rating Curve= 0 ,0
Exp/Cntr=0.3,0.1

Type RM Length L Ch R = 1 ,98599   ,539,539,539
BEGIN DESCRIPTION:
Johnson Creek 128.0
END DESCRIPTION:
XS GIS Cut Line= 3
        1840425.     13980674.95        1840425.       13980275.
        1840375.     13979775.05
#Sta/Elev= 30
  4595.5 2023.74  4695.5 2020.32  4715.5 2018.37  4735.5 2017.62    4786 2012.67
  4939.2 2001.14  4955.5 1998.82  4975.5 1990.32    4998 1988.67  5005.5 1980.83
  5006.5 1980.33  5045.7 1980.83  5048.2 1981.78  5065.8 1983.81  5085.9 1984.75
    5096 1987.02  5116.1 1988.59  5126.1 1990.38  5166.3 1993.77  5206.5 1993.56
  5226.6 1991.42  5266.8 1995.71  5285.3 1996.12    5317 1995.84  5344.7 1993.47
  5357.2 1995.04  5377.3 2001.36  5407.5 2006.83  5437.6 2010.43  5497.9 2013.37
#Mann= 6 ,-1 , 0
  4595.5     .07       0    4786      .1       0  4939.2     .07       0
  5005.5     .05       0  5045.7     .07       0  5285.3      .1       0
Bank Sta=5005.5,5045.7
XS Rating Curve= 0 ,0
Exp/Cntr=0.3,0.1

Type RM Length L Ch R = 1 ,98060   ,568,568,568
BEGIN DESCRIPTION:
Johnson Creek 127.0
END DESCRIPTION:
XS GIS Cut Line= 3
      1841125.01     13980425.02        1840875.       13980025.
      1840675.02     13979675.03
#Sta/Elev= 30
  4528.3 2032.34  4591.1 2025.82  4630.3 2020.62  4645.7 2019.69    4658 2017.05
  4782.4 2000.04  4824.9 1996.94  4840.2 1995.16  4855.6 1991.97  4870.3 1991.49
  4910.9 1987.34  4964.6 1983.53  4971.1 1981.25  4972.3 1979.62  4973.3 1979.12
  5012.5 1979.62  5047.4 1986.86  5085.2 1988.52  5161.3 1988.13  5228.2 1984.32
  5241.9 1986.08  5249.8 1991.69  5252.3 1991.94  5255.6 1992.26  5264.9 1997.92
  5271.4 2003.41  5277.2 2003.48  5308.8 2009.89  5357.8 2012.13  5403.1 2012.17
#Mann= 8 ,-1 , 0
  4528.3     .07       0  4591.1      .1       0  4910.9     .07       0
  4972.3     .05       0  5012.5     .07       0  5047.4    .035       0
  5085.2     .07       0  5252.3      .1       0
Bank Sta=4972.3,5012.5
XS Rating Curve= 0 ,0
Exp/Cntr=0.3,0.1

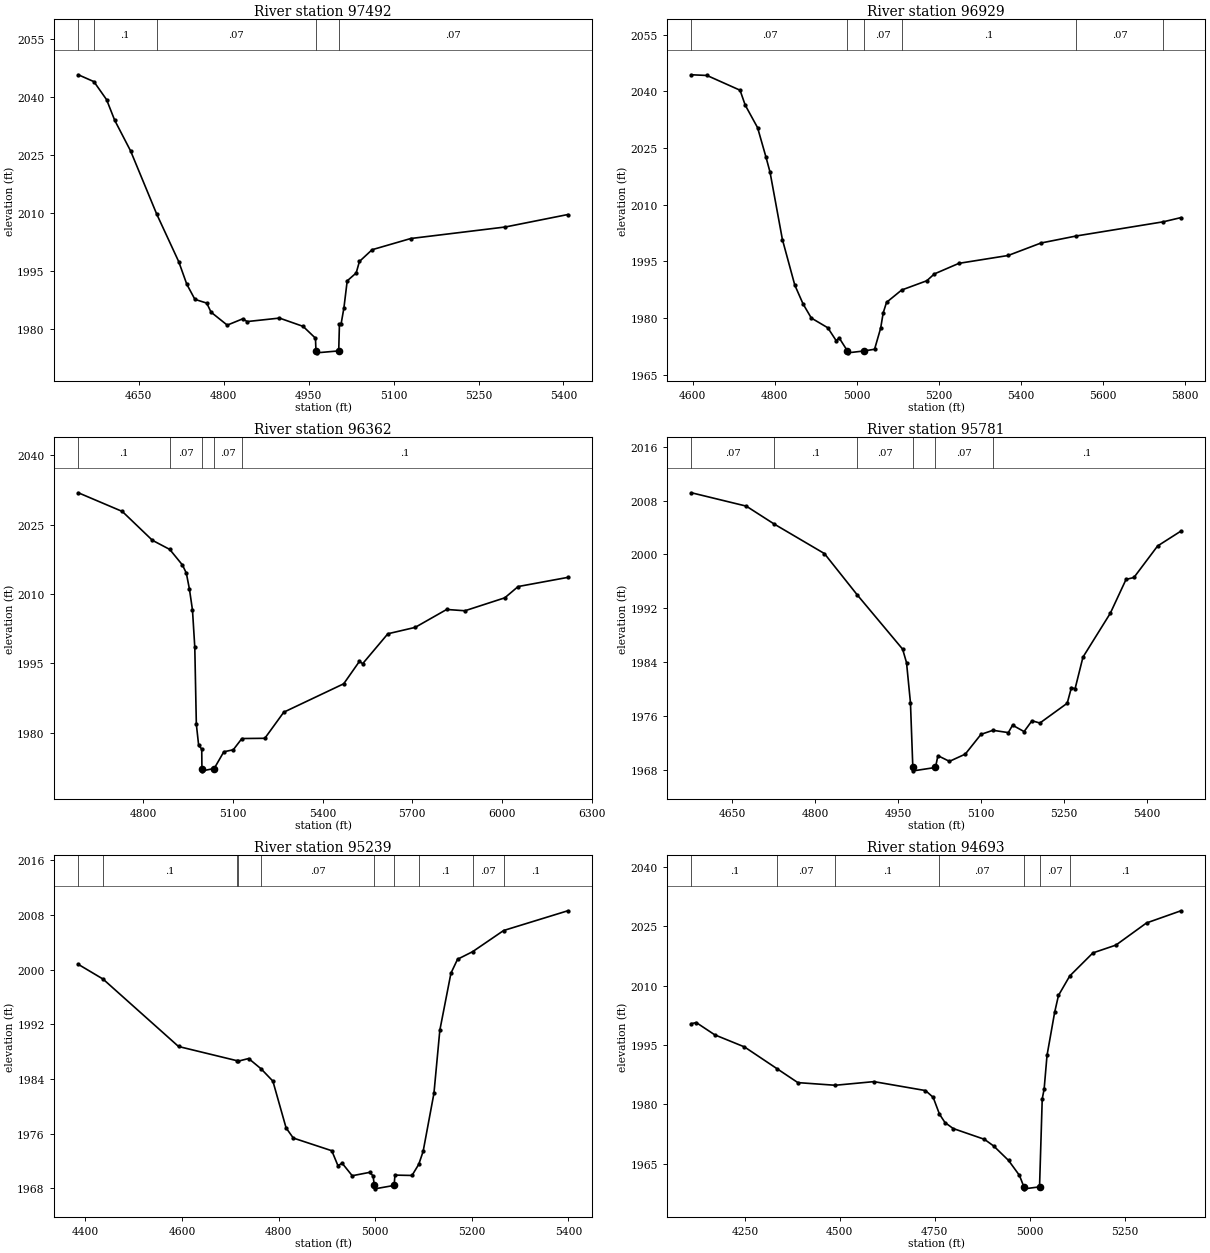
Type RM Length L Ch R = 1 ,97492   ,563,563,563
BEGIN DESCRIPTION:
Johnson Creek 126.0
END DESCRIPTION:
XS GIS Cut Line= 3
        1841625.       13980075.        1841325.       13979725.
      1840974.99       13979525.
#Sta/Elev= 30
  4543.5 2045.77    4571    2044  4593.4 2039.34  4607.7 2034.02  4635.7 2026.12
  4681.9 2009.77  4720.8 1997.47    4735 1991.65  4749.3 1987.75  4770.2 1986.78
  4777.8 1984.44  4806.4 1981.09  4833.8 1982.72  4841.5 1982.01  4898.6 1982.91
  4940.3 1980.77  4962.2 1977.71    4963 1974.43    4964 1973.93  5003.2 1974.43
  5004.5 1981.39  5007.4 1981.39  5012.4 1985.56  5018.2 1992.53    5034 1994.56
  5039.8 1997.54  5062.1 2000.57  5130.5 2003.47  5297.5 2006.45  5407.6 2009.66
#Mann= 5 ,-1 , 0
  4543.5     .07       0    4571      .1       0  4681.9     .07       0
    4963     .05       0  5003.2     .07       0
Bank Sta=4963,5003.2
XS Rating Curve= 0 ,0
Exp/Cntr=0.3,0.1

Type RM Length L Ch R = 1 ,96929   ,567,567,567
BEGIN DESCRIPTION:
Johnson Creek 125.0
END DESCRIPTION:
XS GIS Cut Line= 4
        1841875.     13979924.98        1841825.       13979525.
      1841686.43     13979430.68       1841063.8     13979451.75
#Sta/Elev= 30
  4596.8 2044.41  4634.6 2044.23  4715.2 2040.32  4727.8 2036.38    4758  2030.4
  4778.2 2022.71  4788.3 2018.65  4818.5 2000.79  4848.7 1988.73  4868.9 1983.73
    4889    1980  4929.3 1977.41  4949.5 1974.03  4957.1 1974.71  4977.2 1971.28
  4978.2 1970.78  5017.5 1971.28  5043.3 1971.73  5058.2 1977.34  5064.3 1981.35
  5072.5 1984.15  5109.3 1987.41  5170.7 1989.87    5189 1991.67    5249 1994.48
  5369.1 1996.56  5449.1 1999.86  5535.5 2001.73  5747.5 2005.48  5790.5 2006.59
#Mann= 6 ,-1 , 0
  4596.8     .07       0  4977.2     .05       0  5017.5     .07       0
  5109.3      .1       0  5535.5     .07       0  5747.5      .1       0
Bank Sta=4977.2,5017.5
XS Rating Curve= 0 ,0
Exp/Cntr=0.3,0.1

Type RM Length L Ch R = 1 ,96362   ,581,581,581
BEGIN DESCRIPTION:
Johnson Creek 124.0
END DESCRIPTION:
XS GIS Cut Line= 4
        1842275.     13979575.01        1842175.       13979175.
        1841575.       13978975.      1841049.37     13978705.87
#Sta/Elev= 30
  4584.1 2031.91    4731 2027.87  4831.5 2021.63  4889.6 2019.65    4932 2016.28
  4944.9 2014.53  4955.2 2011.11  4965.5 2006.54  4973.2 1998.52  4978.4 1981.83
  4986.1 1977.27  4996.4 1976.45  4997.1 1972.24  4998.1 1971.74    5038 1972.24
  5070.2 1975.86  5101.8  1976.3  5130.6 1978.73  5207.2 1978.78  5270.5 1984.43
  5470.8 1990.58  5523.5 1995.45    5534 1994.92  5618.3  2001.4  5709.4 2002.78
  5814.8 2006.66  5875.8 2006.38    6009 2009.18  6053.5 2011.62  6219.4  2013.6
#Mann= 5 ,-1 , 0
  4584.1      .1       0  4889.6     .07       0  4997.1     .05       0
    5038     .07       0  5130.6      .1       0
Bank Sta=4997.1,5038
XS Rating Curve= 0 ,0
Exp/Cntr=0.3,0.1

Type RM Length L Ch R = 1 ,95781   ,542,542,542
BEGIN DESCRIPTION:
Johnson Creek 123.0
END DESCRIPTION:
XS GIS Cut Line= 3
        1842575.       13978925.        1842275.       13978625.
      1841925.04     13978325.03
#Sta/Elev= 30
  4576.3 2009.15  4675.3 2007.17    4726  2004.5  4816.7 2000.12  4876.5 1993.94
  4958.1 1985.93  4965.2 1983.92  4972.3 1977.98  4976.6 1968.35  4977.6 1967.85
  5017.5 1968.35    5022  1970.1  5042.8 1969.26  5071.4 1970.33  5099.9 1973.27
  5121.5 1973.87  5149.3 1973.53    5157 1974.63  5177.8 1973.68  5192.1 1975.29
  5206.4 1974.95  5255.8 1977.89  5263.4 1980.22    5270 1980.03  5284.3 1984.74
  5333.7 1991.25  5362.2 1996.28  5376.5 1996.57  5419.3 2001.25  5461.5 2003.46
#Mann= 6 ,-1 , 0
  4576.3     .07       0    4726      .1       0  4876.5     .07       0
  4976.6     .05       0  5017.5     .07       0  5121.5      .1       0
Bank Sta=4976.6,5017.5
XS Rating Curve= 0 ,0
Exp/Cntr=0.3,0.1

Type RM Length L Ch R = 1 ,95239   ,546,546,546
BEGIN DESCRIPTION:
Johnson Creek 122.0
END DESCRIPTION:
XS GIS Cut Line= 3
      1842674.97     13978624.96        1842325.       13978125.
      1841974.99       13977925.
#Sta/Elev= 30
  4385.3 2000.78  4436.4 1998.63  4592.8 1988.75  4714.3 1986.66  4716.9 1986.61
  4737.9 1986.99  4763.7 1985.48  4788.1 1983.68  4815.5 1976.82  4830.4 1975.34
  4910.1 1973.48  4922.8  1971.3  4931.5 1971.66  4952.4 1969.82  4988.2 1970.31
  4995.6 1969.81  4998.1  1968.4  4999.1  1967.9  5039.1  1968.4  5040.9 1969.91
  5076.2 1969.86  5090.2  1971.5  5099.2 1973.38  5121.6 1981.89  5133.8 1991.14
  5156.8 1999.49  5170.5 2001.53  5201.7 2002.64  5265.9 2005.74  5398.7 2008.63
#Mann= 10 ,-1 , 0
  4385.3     .07       0  4436.4      .1       0  4714.3     .07       0
  4716.9      .1       0  4763.7     .07       0  4998.1     .05       0
  5039.1     .07       0  5090.2      .1       0  5201.7     .07       0
  5265.9      .1       0
Bank Sta=4998.1,5039.1
XS Rating Curve= 0 ,0
Exp/Cntr=0.3,0.1

Type RM Length L Ch R = 1 ,94693   ,549,549,549
BEGIN DESCRIPTION:
Johnson Creek 121.0
END DESCRIPTION:
XS GIS Cut Line= 3
      1842867.28      13978577.1        1842625.       13977725.
        1842575.     13977324.99
#Sta/Elev= 30
  4109.3 2000.43  4121.9 2000.69  4170.6 1997.59  4248.7 1994.54  4335.3 1988.98
  4389.4 1985.51  4487.8 1984.84  4589.7 1985.76  4725.5  1983.5  4745.7  1981.8
  4762.4 1977.53  4776.9 1975.41  4798.5  1973.9  4880.8 1971.17  4905.3 1969.47
  4944.4 1965.82    4973 1962.05  4984.7 1959.15  4985.7 1958.65  5025.9 1959.15
    5033 1981.42    5038 1983.86  5045.6 1992.39  5065.7 2003.29  5075.8 2007.56
  5105.4 2012.47  5166.5 2018.31    5227 2020.28  5307.6 2025.88  5398.3 2028.96
#Mann= 7 ,-1 , 0
  4109.3      .1       0  4335.3     .07       0  4487.8      .1       0
  4762.4     .07       0  4984.7     .05       0  5025.9     .07       0
  5105.4      .1       0
Bank Sta=4984.7,5025.9
XS Rating Curve= 0 ,0
Exp/Cntr=0.3,0.1

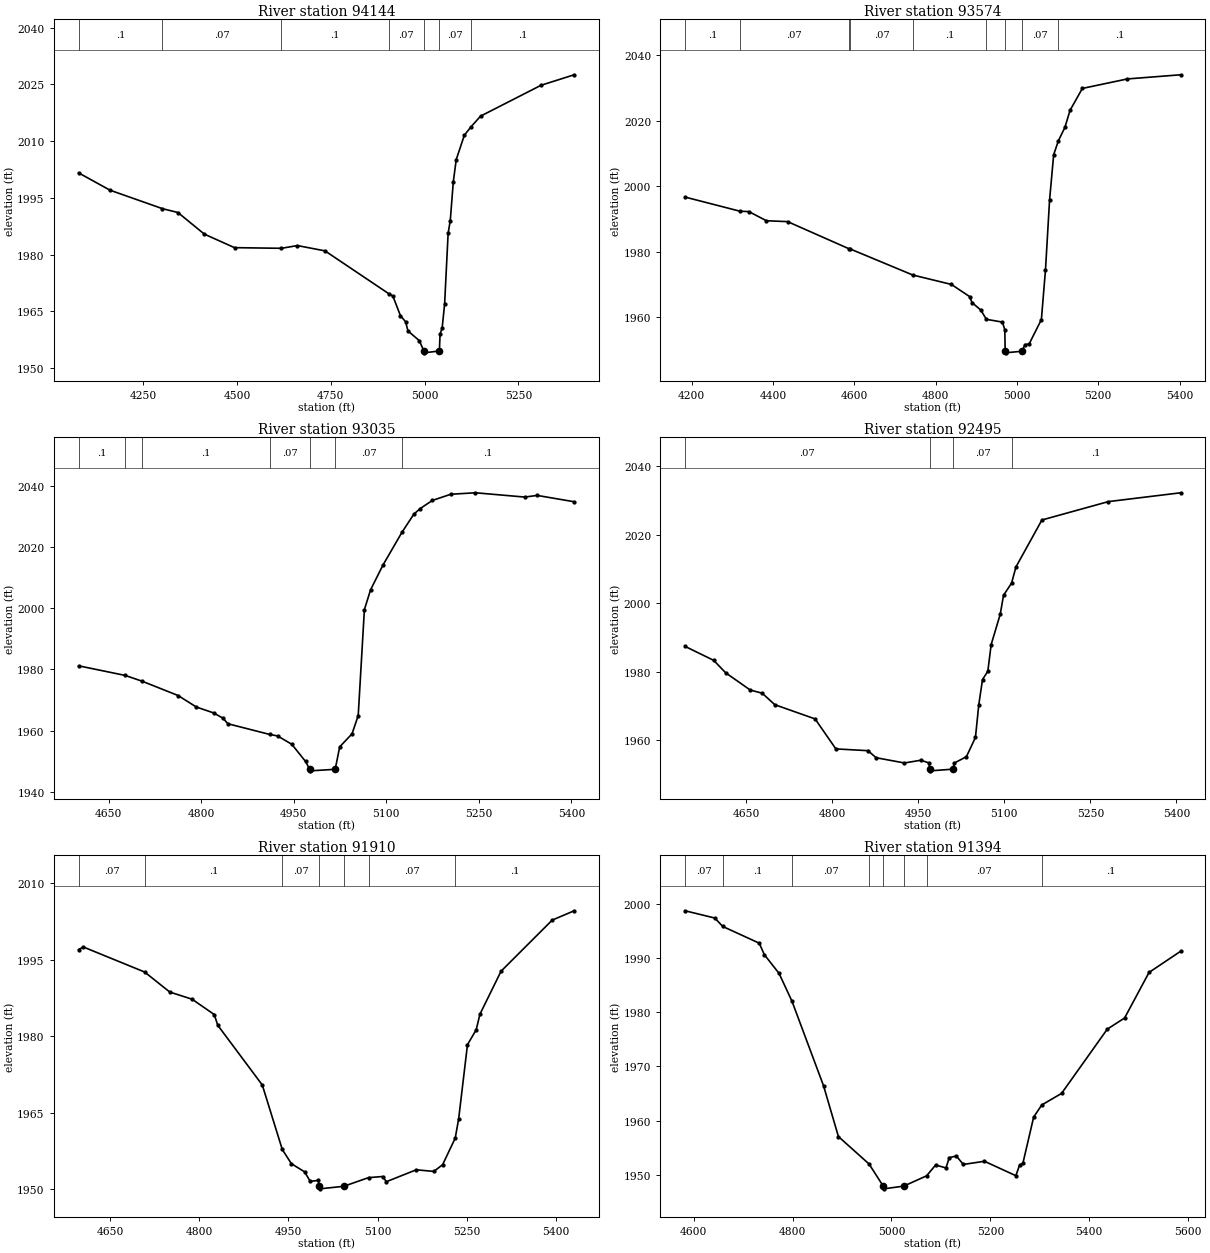
Type RM Length L Ch R = 1 ,94144   ,570,570,570
BEGIN DESCRIPTION:
Johnson Creek 120.0
END DESCRIPTION:
XS GIS Cut Line= 3
      1843028.51     13978588.35        1843125.       13977675.
      1843324.98     13977325.04
#Sta/Elev= 30
  4077.4 2001.58  4161.2    1997  4300.7 1992.13  4342.2  1991.1  4412.6 1985.39
  4493.1 1981.81  4618.4 1981.64  4660.8 1982.36  4734.4 1980.96  4904.4 1969.64
  4915.4 1969.02  4935.5 1963.85  4949.4 1962.21  4955.6  1959.8  4985.8 1957.23
  4998.2  1954.5  4999.2    1954  5039.5  1954.5  5041.2  1958.9  5046.9 1960.61
  5053.4 1966.91  5062.8 1985.63  5068.5 1988.99  5076.5 1999.18  5084.4 2005.11
    5106 2011.53  5123.7 2013.75  5149.2 2016.58  5310.4 2024.74  5398.9 2027.52
#Mann= 7 ,-1 , 0
  4077.4      .1       0  4300.7     .07       0  4618.4      .1       0
  4904.4     .07       0  4998.2     .05       0  5039.5     .07       0
  5123.7      .1       0
Bank Sta=4998.2,5039.5
XS Rating Curve= 0 ,0
Exp/Cntr=0.3,0.1

Type RM Length L Ch R = 1 ,93574   ,539,539,539
BEGIN DESCRIPTION:
Johnson Creek 119.0
END DESCRIPTION:
XS GIS Cut Line= 3
      1843221.03     13978584.13        1843625.       13977875.
      1844024.96       13977825.
#Sta/Elev= 30
  4183.6 1996.72  4318.4 1992.41  4340.6 1992.28  4383.8 1989.49  4435.8 1989.22
  4586.3 1980.96  4590.5 1980.83    4744  1972.9  4838.6 1970.04  4883.7 1966.31
  4889.5 1964.49  4911.1 1962.21  4924.9 1959.37  4964.4 1958.52  4970.2 1956.16
  4971.1 1949.63  4972.1 1949.13  5012.4 1949.63  5019.9 1951.66    5030 1951.83
  5060.2  1959.3  5070.3  1974.5  5080.3 1995.78  5090.4 2009.66    5102 2013.92
  5118.1 2018.03  5130.7 2023.23    5161 2029.92  5271.8 2032.82  5402.8 2034.09
#Mann= 9 ,-1 , 0
  4183.6      .1       0  4318.4     .07       0  4586.3      .1       0
  4590.5     .07       0    4744      .1       0  4924.9     .07       0
  4971.1     .05       0  5012.4     .07       0    5102      .1       0
Bank Sta=4971.1,5012.4
XS Rating Curve= 0 ,0
Exp/Cntr=0.3,0.1

Type RM Length L Ch R = 1 ,93035   ,540,540,540
BEGIN DESCRIPTION:
Johnson Creek 118.0
END DESCRIPTION:
XS GIS Cut Line= 3
        1843625.       13978475.        1843975.       13978275.
      1844374.99       13978275.
#Sta/Elev= 30
  4601.5 1981.15  4676.9 1978.02  4703.8 1976.17  4762.7 1971.46  4792.3  1967.7
  4820.3 1965.78  4835.4 1964.06  4843.4 1962.24    4911 1958.76    4924 1958.26
    4947 1955.53  4969.3 1949.92    4976 1947.37    4977 1946.87  5017.3 1947.37
  5024.6  1954.7  5044.6 1958.96  5054.6  1964.9  5064.6 1999.48  5074.6 2005.95
  5094.6    2014  5125.5 2024.74  5144.6 2030.61  5154.6 2032.42  5174.6 2035.12
  5204.6 2037.16  5244.6 2037.64  5324.6 2036.24  5344.6 2036.78  5404.6 2034.71
#Mann= 7 ,-1 , 0
  4601.5      .1       0  4676.9     .07       0  4703.8      .1       0
    4911     .07       0    4976     .05       0  5017.3     .07       0
  5125.5      .1       0
Bank Sta=4976,5017.3
XS Rating Curve= 0 ,0
Exp/Cntr=0.3,0.1

Type RM Length L Ch R = 1 ,92495   ,585,585,585
BEGIN DESCRIPTION:
Johnson Creek 117.0
END DESCRIPTION:
XS GIS Cut Line= 3
      1843874.99     13979025.01        1844225.       13978725.
        1844425.       13978375.
#Sta/Elev= 30
  4543.4 1987.43  4593.3 1983.35  4614.2 1979.71    4657 1974.68  4677.9 1973.75
  4699.8  1970.4  4770.1 1966.24  4806.3 1957.48  4862.3 1956.96  4876.5  1954.9
  4925.9 1953.37  4954.4 1954.17  4968.7 1953.38    4970 1951.57    4971 1951.07
  5011.4 1951.57  5012.3 1953.31  5033.9 1955.19  5049.7 1960.83  5055.5 1970.38
    5062 1977.73  5071.3 1980.18  5077.1 1987.97  5092.9 1996.81  5098.7 2002.38
  5112.7 2005.92  5120.3 2010.64  5165.6 2024.37  5281.5 2029.74  5407.5 2032.32
#Mann= 4 ,-1 , 0
  4543.4     .07       0    4970     .05       0  5011.4     .07       0
  5112.7      .1       0
Bank Sta=4970,5011.4
XS Rating Curve= 0 ,0
Exp/Cntr=0.3,0.1

Type RM Length L Ch R = 1 ,91910   ,516,516,516
BEGIN DESCRIPTION:
Johnson Creek 116.0
END DESCRIPTION:
XS GIS Cut Line= 3
      1843975.04     13979474.98        1844325.       13979275.
      1844575.01     13978924.99
#Sta/Elev= 30
  4597.4    1997  4605.3 1997.51  4708.3  1992.6  4750.7 1988.66  4788.1 1987.26
  4825.5 1984.24  4831.3 1982.14  4906.2 1970.41  4939.8 1957.75  4955.1 1954.96
  4977.4 1953.35  4986.8 1951.49  5000.5 1951.68  5001.9 1950.52  5002.9 1950.02
  5043.3 1950.52  5084.8 1952.22  5108.6 1952.44  5114.8 1951.42  5165.1 1953.76
  5194.6 1953.44  5209.4 1954.76  5230.6 1959.98  5236.4 1963.79  5251.2 1978.33
  5265.9 1981.26  5272.1  1984.3  5307.7 1992.76  5393.7 2002.79  5430.6 2004.62
#Mann= 7 ,-1 , 0
  4597.4     .07       0  4708.3      .1       0  4939.8     .07       0
  5001.9     .05       0  5043.3     .07       0  5084.8     .07       0
  5230.6      .1       0
Bank Sta=5001.9,5043.3
XS Rating Curve= 0 ,0
Exp/Cntr=0.3,0.1

Type RM Length L Ch R = 1 ,91394   ,575,575,575
BEGIN DESCRIPTION:
Johnson Creek 115.0
END DESCRIPTION:
XS GIS Cut Line= 3
      1844075.03       13979725.        1844475.       13979725.
      1844924.97     13979325.03
#Sta/Elev= 30
  4582.8 1998.77  4642.8 1997.43    4659 1995.87  4732.8 1992.78  4742.8 1990.69
  4772.8  1987.2  4798.9 1982.06  4862.8 1966.42  4892.8 1957.05  4954.8 1951.98
  4983.4 1947.89  4984.4 1947.39  5024.8 1947.89  5071.1 1949.79  5089.4  1951.8
  5110.3 1951.25    5117 1953.15  5131.2 1953.46  5145.4  1951.9  5188.1 1952.48
  5251.6 1949.82  5259.1 1951.76  5265.8  1952.1  5287.6 1960.65    5304 1962.89
    5344 1965.02  5436.4 1976.89  5471.5 1978.96  5520.9 1987.38  5584.8 1991.29
#Mann= 8 ,-1 , 0
  4582.8     .07       0    4659      .1       0  4798.9     .07       0
  4954.8     .07       0  4983.4     .05       0  5024.8     .07       0
  5071.1     .07       0    5304      .1       0
Bank Sta=4983.4,5024.8
XS Rating Curve= 0 ,0
Exp/Cntr=0.3,0.1

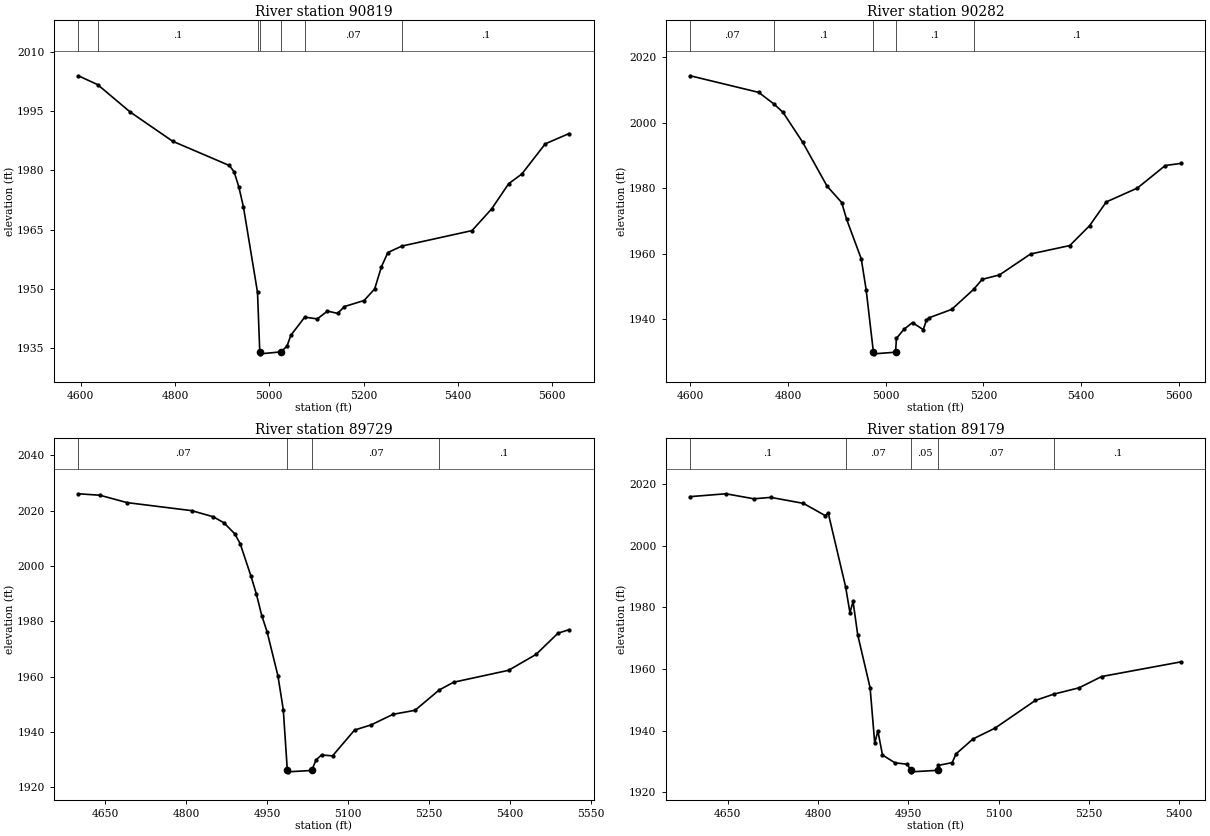
Type RM Length L Ch R = 1 ,90819   ,537,537,537
BEGIN DESCRIPTION:
Johnson Creek 114.0
END DESCRIPTION:
XS GIS Cut Line= 3
        1844825.     13980525.03        1844825.       13980125.
      1845224.98     13979625.03
#Sta/Elev= 30
  4595.2 2003.94  4636.1 2001.69  4705.2 1994.75  4795.2 1987.36  4915.2 1981.23
  4925.2 1979.67  4935.2  1975.9  4945.2 1970.72    4975 1949.12  4979.8 1934.05
  4980.8 1933.55    5025 1934.05  5037.6 1935.53  5045.7 1938.25  5075.2 1942.85
  5101.7 1942.39  5123.3 1944.37  5144.9 1943.79  5159.3 1945.52  5200.9 1947.05
  5223.3 1949.96  5237.7 1955.57  5251.4  1959.2  5281.1 1960.83  5429.8 1964.75
  5471.5 1970.25  5507.5 1976.62  5535.5 1979.08  5585.1 1986.71  5635.5 1989.31
#Mann= 7 ,-1 , 0
  4595.2     .07       0  4636.1      .1       0    4975     .07       0
  4979.8     .05       0    5025     .07       0  5075.2     .07       0
  5281.1      .1       0
Bank Sta=4979.8,5025
XS Rating Curve= 0 ,0
Exp/Cntr=0.3,0.1

Type RM Length L Ch R = 1 ,90282   ,553,553,553
BEGIN DESCRIPTION:
Johnson Creek 113.0
END DESCRIPTION:
XS GIS Cut Line= 3
        1845275.       13980775.        1845275.       13980375.
      1845525.02     13979824.96
#Sta/Elev= 30
    4600 2014.32    4740 2009.26  4771.8 2005.65    4790 2003.14    4830 1994.06
    4880 1980.65    4910 1975.63    4920 1970.54    4950 1958.47    4960 1949.06
  4974.9 1929.97  4975.9 1929.47  5020.2 1929.97    5022 1934.18  5037.3 1936.95
  5054.9 1939.01  5076.9 1936.84  5083.5 1939.72    5089 1940.49  5135.1 1943.03
  5179.8 1949.12  5197.7 1952.21  5232.9 1953.55  5296.6 1959.94  5376.8 1962.51
  5417.4 1968.59  5451.5 1975.82  5515.2 1980.06  5572.3 1986.94  5604.2 1987.58
#Mann= 5 ,-1 , 0
    4600     .07       0  4771.8      .1       0  4974.9     .05       0
  5020.2      .1       0  5179.8      .1       0
Bank Sta=4974.9,5020.2
XS Rating Curve= 0 ,0
Exp/Cntr=0.3,0.1

Type RM Length L Ch R = 1 ,89729   ,550,550,550
BEGIN DESCRIPTION:
Johnson Creek 112.0
END DESCRIPTION:
XS GIS Cut Line= 3
        1845775.     13980924.99        1845775.       13980525.
        1845675.     13980024.99
#Sta/Elev= 30
  4600.1 2026.06  4640.1 2025.53  4690.1 2022.88  4810.1 2019.97  4850.1 2017.76
  4870.1 2015.57  4890.1 2011.59  4900.1 2008.07  4920.1 1996.35  4930.1 1989.92
  4940.1 1982.09  4950.1 1976.17  4970.1 1960.36  4980.1 1948.07  4987.6 1926.12
  4988.6 1925.62  5032.9 1926.12  5040.9 1929.98  5051.1 1931.71  5071.5 1931.39
  5112.3 1940.72  5142.9 1942.57  5183.7  1946.4  5224.4 1947.85  5269.1 1955.16
  5295.8 1957.98  5397.8 1962.29  5448.8 1968.03  5489.6 1975.71    5510 1976.97
#Mann= 4 ,-1 , 0
  4600.1     .07       0  4987.6     .05       0  5032.9     .07       0
  5269.1      .1       0
Bank Sta=4987.6,5032.9
XS Rating Curve= 0 ,0
Exp/Cntr=0.3,0.1

Type RM Length L Ch R = 1 ,89179   ,585,585,585
BEGIN DESCRIPTION:
Johnson Creek 111.0
END DESCRIPTION:
XS GIS Cut Line= 3
        1846175.     13980774.99        1846275.       13980375.
      1846075.01     13980025.01
#Sta/Elev= 30
  4587.7 2015.88    4647  2016.8  4693.3 2015.18  4721.7 2015.63  4775.8 2013.69
  4811.9 2009.74    4817 2010.57  4845.8 1986.74  4853.1 1978.27  4858.3 1981.89
    4866  1971.1  4886.6 1953.93  4894.3 1935.94  4899.5 1939.98  4907.2 1932.13
  4927.8 1929.62  4948.5 1929.13  4954.2 1927.18  4955.2 1926.68  4999.5 1927.18
    5000 1928.77    5023 1929.66  5029.5 1932.52  5057.6 1937.33  5094.3 1940.85
  5161.2 1949.82    5192 1951.87    5234 1953.92  5271.4 1957.57  5403.1 1962.32
#Mann= 5 ,-1 , 0
  4587.7      .1       0  4845.8     .07       0  4954.2     .05       0
  4999.5     .07       0    5192      .1       0
Bank Sta=4954.2,4999.5
XS Rating Curve= 0 ,0
Exp/Cntr=0.3,0.1