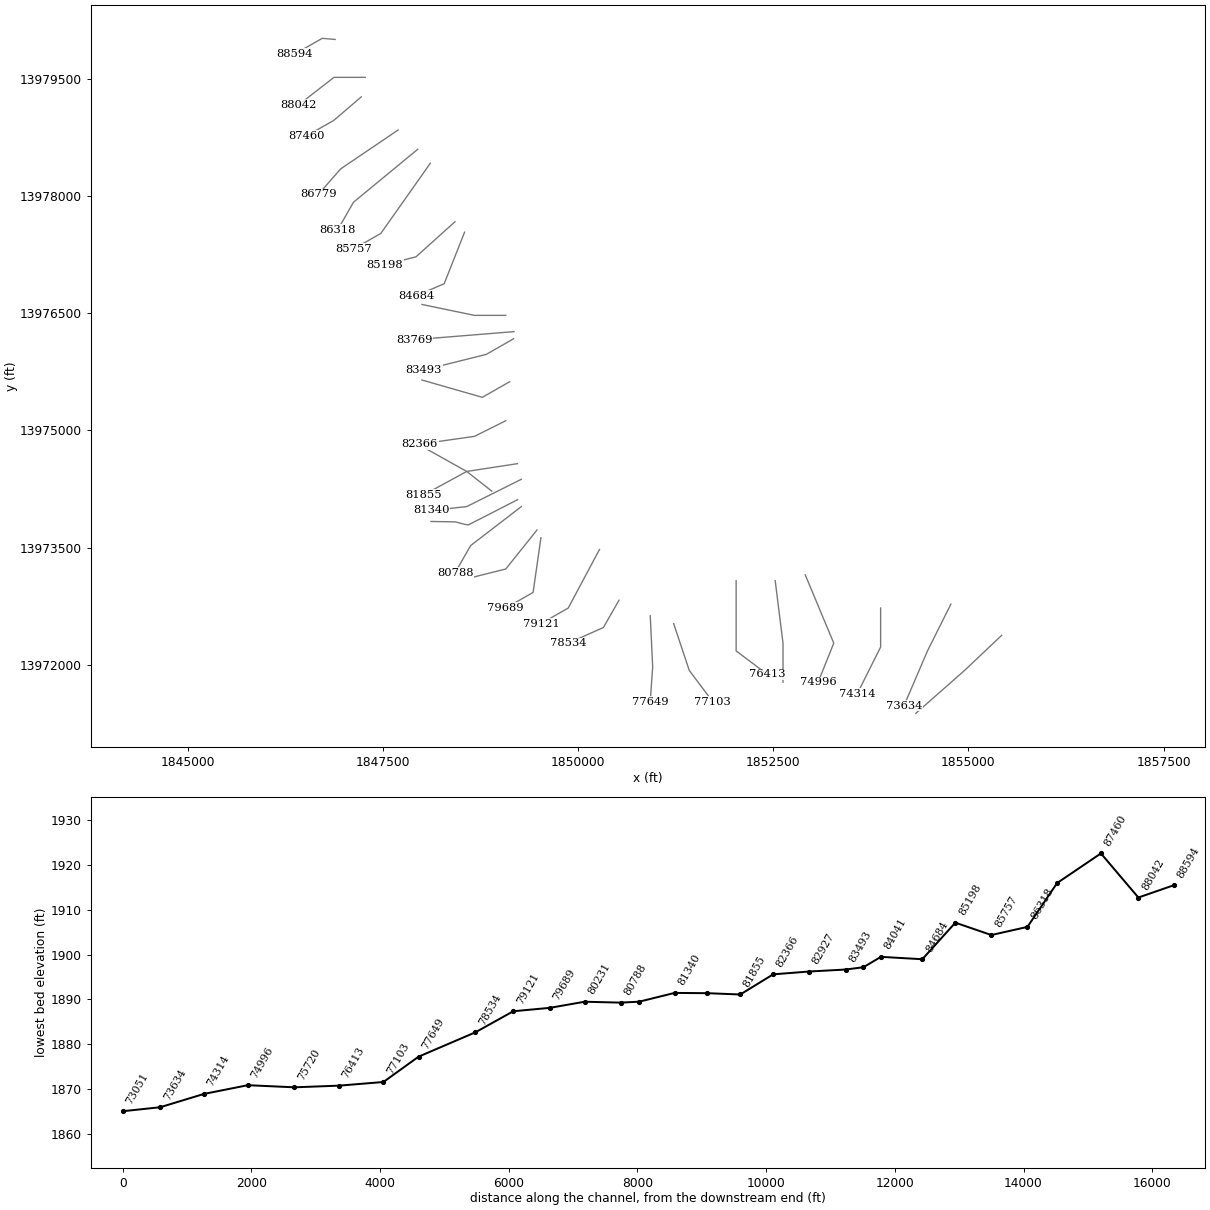
HEC-RAS study Johnson Creek.prj: Johnson Creek Base Level Engineering

--- Johnson Creek.g01 (geometry) --- (continued)

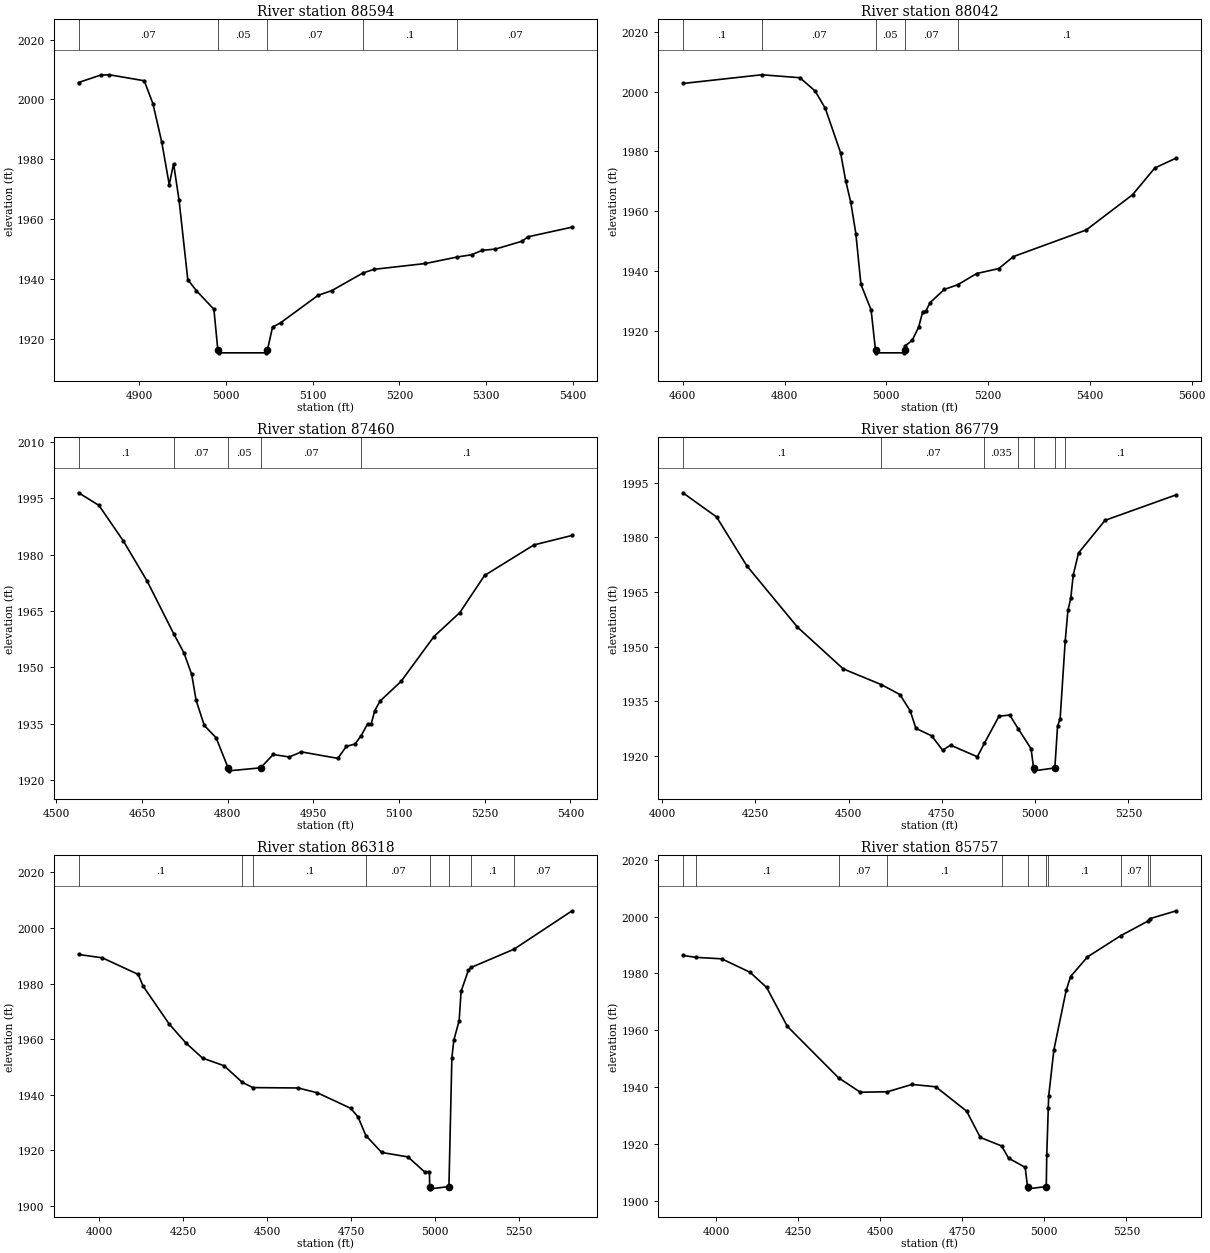
Type RM Length L Ch R = 1 ,88594   ,552,552,552
BEGIN DESCRIPTION:
Johnson Creek 110.0
END DESCRIPTION:
XS GIS Cut Line= 3
       1846890.5     13980010.64        1846725.       13980025.
      1846375.03     13979825.02
#Sta/Elev= 30
  4829.9 2005.67  4855.5 2008.15  4865.5 2008.25  4905.7 2006.25  4915.7 1998.58
  4925.8 1985.87  4934.5 1971.57  4939.5 1978.54  4945.8 1966.45  4955.9 1939.85
  4965.9 1936.13    4986 1929.96  4990.6 1916.21  4991.9 1915.41  5046.2 1915.41
  5047.6 1916.21  5053.6 1923.97    5063 1925.46  5106.2 1934.62    5122 1936.19
  5158.2 1942.13  5170.9  1943.3    5230 1945.24  5266.7 1947.41  5283.2 1948.16
  5295.5 1949.64  5310.6 1950.05  5341.5 1952.69    5348 1954.14  5399.1 1957.38
#Mann= 5 ,-1 , 0
  4829.9     .07       0  4990.6     .05       0  5047.6     .07       0
  5158.2      .1       0  5266.7     .07       0
Bank Sta=4990.6,5047.6
XS Rating Curve= 0 ,0
Exp/Cntr=0.3,0.1

Type RM Length L Ch R = 1 ,88042   ,582,582,582
BEGIN DESCRIPTION:
Johnson Creek 109.0
END DESCRIPTION:
XS GIS Cut Line= 3
      1847275.01       13979525.        1846875.       13979525.
        1846425.       13979175.
#Sta/Elev= 30
    4600 2002.68    4755 2005.59    4830 2004.61    4860 2000.17    4880 1994.36
    4910 1979.54    4920 1970.23    4930 1963.01    4940 1952.53    4950 1935.54
    4970 1927.01  4978.7 1913.47    4980 1912.67  5034.4 1912.67  5035.7 1913.47
  5036.2 1914.92  5050.7 1916.82  5063.3 1921.21  5071.5 1926.41  5077.8 1926.66
    5086 1929.48    5114 1933.87  5140.6 1935.45  5177.4 1939.17  5220.8 1940.83
  5249.8 1944.84  5392.7 1953.72  5484.1 1965.54  5527.6 1974.44  5570.1  1977.8
#Mann= 5 ,-1 , 0
    4600      .1       0    4755     .07       0  4978.7     .05       0
  5035.7     .07       0  5140.6      .1       0
Bank Sta=4978.7,5035.7
XS Rating Curve= 0 ,0
Exp/Cntr=0.3,0.1

Type RM Length L Ch R = 1 ,87460   ,681,681,681
BEGIN DESCRIPTION:
Johnson Creek 108.0
END DESCRIPTION:
XS GIS Cut Line= 3
      1847225.01     13979275.01        1846875.       13978975.
        1846525.       13978775.
#Sta/Elev= 30
    4539 1996.48  4574.7 1993.13  4617.5 1983.65  4659.2 1972.95  4705.4 1959.03
  4723.4 1953.91  4737.1 1948.16  4744.8 1941.28  4759.1 1934.58  4779.9 1931.26
  4800.8 1923.28  4802.1 1922.48  4857.8 1923.28  4879.8 1926.83  4907.8 1926.17
  4929.2 1927.52  4992.9  1925.8  5007.9    1929    5023 1929.61  5033.5  1931.8
  5045.3 1935.02  5051.1 1934.84  5057.6 1938.52  5066.9 1941.04  5103.6 1946.28
  5161.2 1958.22  5206.6 1964.61  5249.8 1974.47  5336.2  1982.6  5403.1 1985.13
#Mann= 5 ,-1 , 0
    4539      .1       0  4705.4     .07       0  4800.8     .05       0
  4857.8     .07       0  5033.5      .1       0
Bank Sta=4800.8,4857.8
XS Rating Curve= 0 ,0
Exp/Cntr=0.3,0.1

Type RM Length L Ch R = 1 ,86779   ,461,461,461
BEGIN DESCRIPTION:
Johnson Creek 107.0
END DESCRIPTION:
XS GIS Cut Line= 3
       1847696.9     13978850.63      1846960.93     13978352.24
        1846675.       13978025.
#Sta/Elev= 30
  4055.6 1992.22  4145.9 1985.59    4227 1972.19  4362.9 1955.34  4485.7 1943.87
    4588 1939.55  4637.6 1936.84  4665.4 1932.32  4680.4 1927.55  4722.4 1925.52
  4752.3 1921.55  4773.3 1922.95  4845.2 1919.75  4864.2 1923.48  4903.3 1930.89
    4932  1931.2    4955  1927.4  4989.3 1921.95  4995.9 1916.69  4997.2 1915.89
    5053 1916.69  5060.3 1928.17  5067.2 1930.23  5080.8 1951.55  5088.1 1959.95
  5095.7  1963.3  5102.3 1969.64  5116.5  1975.7  5187.7 1984.66    5379 1991.68
#Mann= 7 ,-1 , 0
  4055.6      .1       0    4588     .07       0  4864.2    .035       0
    4955     .07       0  4995.9     .05       0    5053     .07       0
  5080.8      .1       0
Bank Sta=4995.9,5053
XS Rating Curve= 0 ,0
Exp/Cntr=0.3,0.1

Type RM Length L Ch R = 1 ,86318   ,561,561,561
BEGIN DESCRIPTION:
Johnson Creek 106.0
END DESCRIPTION:
XS GIS Cut Line= 3
      1847947.23     13978602.91        1847125.       13977925.
      1846924.98     13977574.97
#Sta/Elev= 30
  3938.8 1990.47  4009.6 1989.26  4116.5 1983.29  4130.8 1979.12    4209 1965.37
  4258.5  1958.6    4308 1953.17  4371.8 1950.44  4426.2 1944.45  4457.8 1942.57
    4592 1942.43  4649.4 1940.71  4748.4 1935.14  4770.6 1932.02  4793.7 1925.33
  4840.9 1919.23  4919.1 1917.63  4968.6 1912.23  4982.9 1912.36  4983.8 1906.94
  4985.1 1906.14    5041 1906.94  5049.8 1953.35  5055.6 1959.66  5071.4 1966.62
  5077.2  1977.2  5098.8 1984.74  5107.7 1985.83  5234.9 1992.38  5407.6 2006.19
#Mann= 8 ,-1 , 0
  3938.8      .1       0  4426.2     .07       0  4457.8      .1       0
  4793.7     .07       0  4983.8     .05       0    5041     .07       0
  5107.7      .1       0  5234.9     .07       0
Bank Sta=4983.8,5041
XS Rating Curve= 0 ,0
Exp/Cntr=0.3,0.1

Type RM Length L Ch R = 1 ,85757   ,559,559,559
BEGIN DESCRIPTION:
Johnson Creek 105.0
END DESCRIPTION:
XS GIS Cut Line= 3
      1848109.41     13978425.12        1847475.       13977525.
      1847125.03     13977325.02
#Sta/Elev= 30
  3898.3 1986.31  3938.6 1985.65  4016.7 1985.13  4102.9 1980.42  4153.5  1975.1
  4216.5 1961.44  4372.7 1943.34  4439.1 1938.27  4521.8 1938.43  4596.8 1941.01
  4669.2 1940.17  4763.1 1931.63  4804.9 1922.38  4869.8 1919.39  4891.1  1915.1
  4941.6 1911.89  4948.7 1905.13  4950.1 1904.33  5005.9 1905.13  5007.4 1916.21
    5012 1932.57  5013.2 1936.84    5029 1953.08  5066.5 1974.02  5080.1  1978.9
  5131.3  1985.8  5232.4 1993.22  5315.6 1998.38  5321.7 1999.24  5402.6 2002.01
#Mann= 11 ,-1 , 0
  3898.3     .07       0  3938.6      .1       0  4372.7     .07       0
  4521.8      .1       0  4869.8     .07       0  4948.7     .05       0
  5005.9     .07       0    5012      .1       0  5232.4     .07       0
  5315.6      .1       0  5321.7     .07       0
Bank Sta=4948.7,5005.9
XS Rating Curve= 0 ,0
Exp/Cntr=0.3,0.1

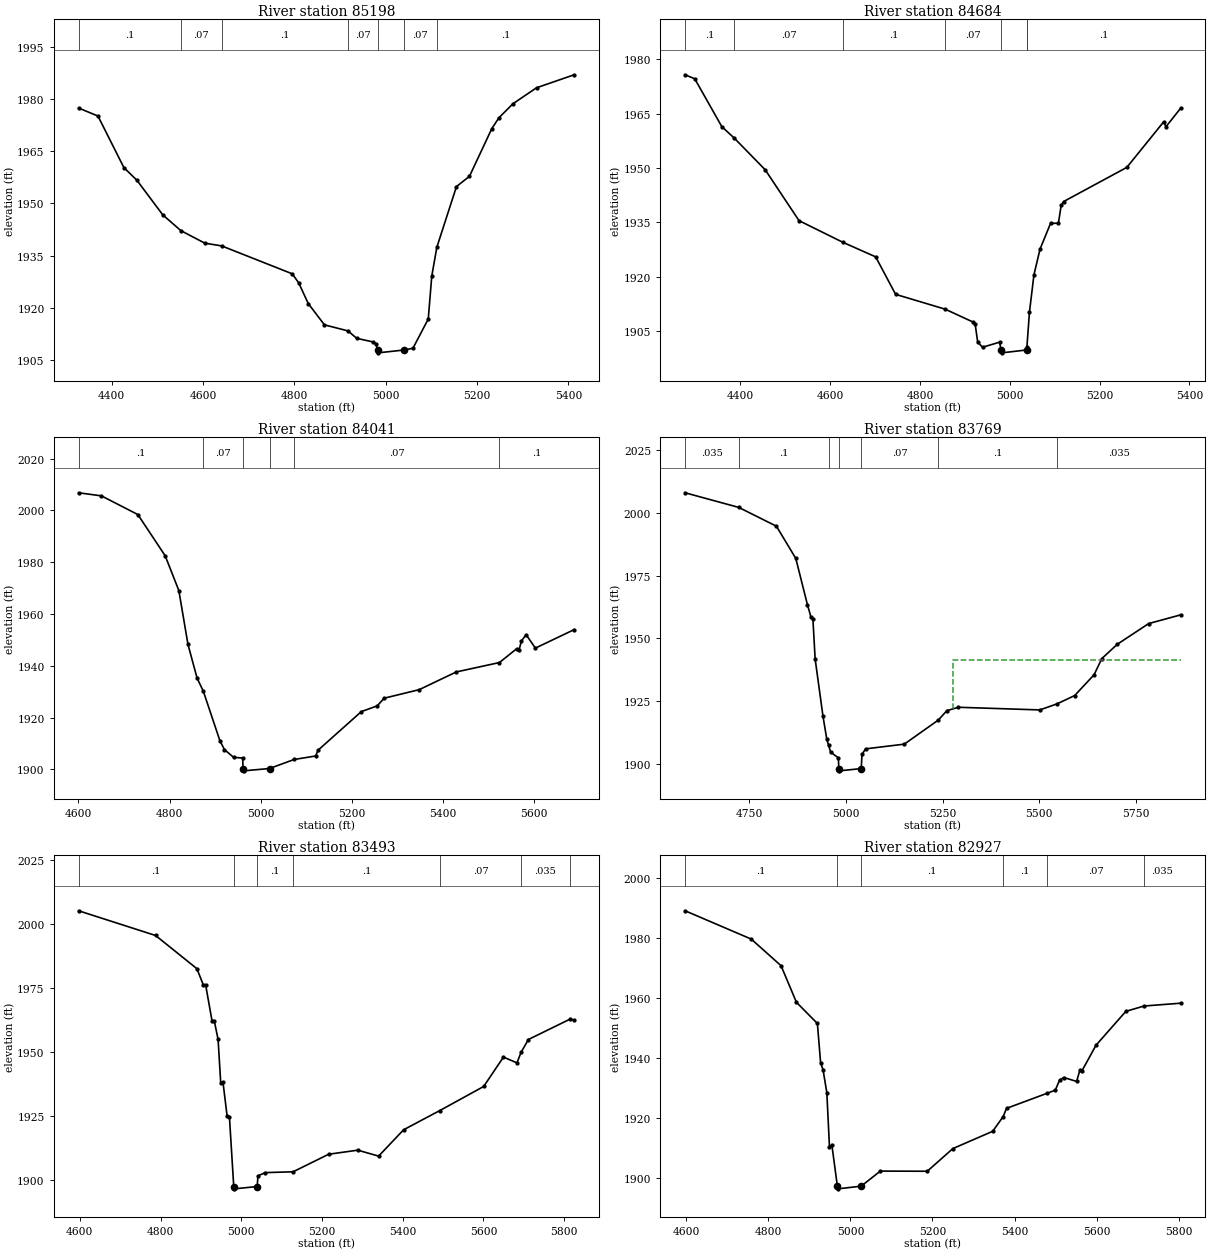
Type RM Length L Ch R = 1 ,85198   ,514,514,514
BEGIN DESCRIPTION:
Johnson Creek 104.0
END DESCRIPTION:
XS GIS Cut Line= 3
      1848425.03     13977675.03        1847925.       13977225.
      1847525.04     13977125.01
#Sta/Elev= 30
  4327.5 1977.41  4369.8 1975.12  4426.6  1960.3    4455 1956.68  4511.8 1946.71
  4551.4 1942.19  4603.7 1938.59  4640.6 1937.81  4795.1 1929.79  4809.3 1927.21
  4830.2 1921.25  4865.7 1915.12  4917.4 1913.38  4936.3 1911.25  4972.2 1910.21
  4978.9 1909.63  4981.9 1907.88  4983.2 1907.08  5039.1 1907.88  5059.5  1908.4
    5093 1916.79  5100.7 1929.11  5111.8 1937.41  5154.8 1954.86  5183.2 1957.79
  5232.2 1971.51  5247.6  1974.6  5278.5 1978.65  5330.1 1983.24  5412.5 1986.97
#Mann= 7 ,-1 , 0
  4327.5      .1       0  4551.4     .07       0  4640.6      .1       0
  4917.4     .07       0  4981.9     .05       0  5039.1     .07       0
  5111.8      .1       0
Bank Sta=4981.9,5039.1
XS Rating Curve= 0 ,0
Exp/Cntr=0.3,0.1

Type RM Length L Ch R = 1 ,84684   ,643,643,643
BEGIN DESCRIPTION:
Johnson Creek 103.0
END DESCRIPTION:
XS GIS Cut Line= 3
      1848547.51     13977540.96      1848286.44     13976880.66
      1847924.98     13976724.99
#Sta/Elev= 30
  4276.7 1975.77  4298.2 1974.66  4358.4 1961.46  4386.4 1958.25    4455 1949.54
  4530.4 1935.47  4627.9  1929.5  4701.1 1925.47  4745.5 1915.11  4855.8 1911.02
  4917.4 1907.49  4922.8 1906.79  4928.3 1901.93  4939.1 1900.49  4976.9 1901.89
  4980.6 1899.75  4981.9 1898.95  5037.8 1899.75    5038 1900.67  5043.6 1910.17
  5053.6 1920.51  5067.1 1927.58  5090.6 1934.72  5108.1 1934.77  5114.2 1939.66
  5119.6 1940.74  5260.5 1950.19  5342.3 1962.74  5347.7 1961.42  5380.3 1966.53
#Mann= 7 ,-1 , 0
  4276.7      .1       0  4386.4     .07       0  4627.9      .1       0
  4855.8     .07       0  4980.6     .05       0  5037.8     .07       0
    5038      .1       0
Bank Sta=4980.6,5037.8
XS Rating Curve= 0 ,0
Exp/Cntr=0.3,0.1

Type RM Length L Ch R = 1 ,84041   ,272,272,272
BEGIN DESCRIPTION:
Johnson Creek 102.0
END DESCRIPTION:
XS GIS Cut Line= 3
      1849075.02       13976475.        1848675.       13976475.
      1848001.67     13976614.74
#Sta/Elev= 30
  4600.3  2006.8  4650.3 2005.61  4730.3 1998.39  4790.3 1982.48  4820.3 1969.04
  4840.3 1948.27  4860.3 1935.27    4874 1930.21  4910.3 1911.16  4920.3 1907.69
  4940.3  1904.7  4960.3 1904.41  4961.3 1900.38  4962.7 1899.48  5019.3 1900.38
  5073.2 1903.86  5120.6 1905.21  5125.7 1907.42  5220.8 1922.34  5255.7 1924.55
    5271 1927.52  5347.6  1930.8  5429.3 1937.65    5524 1941.28  5561.6 1946.59
  5566.7 1945.94  5572.3 1949.62  5582.5 1952.04  5602.9 1946.85    5688 1953.99
#Mann= 6 ,-1 , 0
  4600.3      .1       0    4874     .07       0  4961.3     .05       0
  5019.3     .07       0  5073.2     .07       0    5524      .1       0
Bank Sta=4961.3,5019.3
XS Rating Curve= 0 ,0
Exp/Cntr=0.3,0.1

Type RM Length L Ch R = 1 ,83769   ,276,276,276
BEGIN DESCRIPTION:
Mapping XS b6a6432c
END DESCRIPTION:
XS GIS Cut Line= 2
      1849180.73     13976266.67      1847901.52     13976163.01
#Sta/Elev= 30
  4583.3 2007.96  4722.3 2002.13  4819.8 1994.64    4870  1981.8  4900.1 1963.37
  4909.3 1958.44  4914.3 1957.69  4920.1 1941.74  4940.2 1919.15  4950.2 1909.81
  4954.7 1907.48  4960.3 1904.59  4980.3 1902.35  4981.4 1898.07  4982.8 1897.17
  5039.5 1898.07  5041.4  1903.7  5050.6 1905.93  5150.9  1907.8  5239.1 1917.39
  5261.2 1921.15  5291.3  1922.5    5502 1921.44  5546.5 1923.85  5592.3 1927.17
  5642.5 1935.45  5662.6  1941.9  5702.7 1947.61    5784 1955.85  5866.7 1959.31
#Mann= 7 ,-1 , 0
  4583.3    .035       0  4722.3      .1       0  4954.7     .07       0
  4981.4     .05       0  5039.5     .07       0  5239.1      .1       0
  5546.5    .035       0
#XS Ineff= 2 , 0
                         5277.52          1941.2
Permanent Ineff=
       F       F
Bank Sta=4981.4,5039.5
XS Rating Curve= 0 ,0
Exp/Cntr=0.3,0.1

Type RM Length L Ch R = 1 ,83493   ,566,566,566
BEGIN DESCRIPTION:
Johnson Creek 101.0
END DESCRIPTION:
XS GIS Cut Line= 3
      1849174.98     13976174.99        1848825.       13975975.
      1848025.01       13975775.
#Sta/Elev= 30
    4597  2005.1  4787.7 1995.46    4890 1982.52  4905.8 1976.23  4911.5 1976.32
  4927.4 1962.26  4933.1 1962.12  4942.5 1954.94    4949 1938.06  4954.7 1938.19
  4964.8  1925.1  4970.6 1924.72  4981.3 1897.56  4982.7 1896.66  5039.4 1897.56
  5041.3 1901.73  5059.4 1902.99  5128.3 1903.31  5216.6 1910.16  5288.7 1911.74
  5340.2 1909.42  5402.1 1919.69    5492  1927.2  5600.5 1936.58  5649.5 1948.04
    5683 1945.78    5693 1949.85  5711.3  1954.9  5814.3 1962.83  5824.7 1962.49
#Mann= 7 ,-1 , 0
    4597      .1       0  4981.3     .05       0  5039.4      .1       0
  5128.3      .1       0    5492     .07       0    5693    .035       0
  5814.3     .07       0
Bank Sta=4981.3,5039.4
XS Rating Curve= 0 ,0
Exp/Cntr=0.3,0.1

Type RM Length L Ch R = 1 ,82927   ,561,561,561
BEGIN DESCRIPTION:
Johnson Creek 100.0
END DESCRIPTION:
XS GIS Cut Line= 3
      1849124.99     13975624.99        1848775.       13975425.
      1848001.24     13975646.74
#Sta/Elev= 30
    4597 1989.17  4758.2 1979.71  4830.9 1970.81  4868.4 1958.58  4919.5 1951.49
  4927.4 1938.25  4933.2 1936.08  4942.5 1928.37    4949  1910.1  4954.7 1910.97
  4968.2 1897.12  4969.6 1896.22  5026.3 1897.12  5072.9 1902.15  5187.3  1902.1
  5249.8 1909.68  5346.8 1915.45  5372.4 1920.38  5380.5 1923.12    5480 1928.19
  5499.4  1929.2  5509.8 1932.53  5520.2 1933.43  5551.4 1932.13  5559.7 1936.02
  5564.9 1935.76  5598.6 1944.22  5671.4 1955.54  5715.6 1957.33    5805 1958.28
#Mann= 6 ,-1 , 0
    4597      .1       0  4968.2     .05       0  5026.3      .1       0
  5372.4      .1       0    5480     .07       0  5715.6    .035       0
Bank Sta=4968.2,5026.3
XS Rating Curve= 0 ,0
Exp/Cntr=0.3,0.1

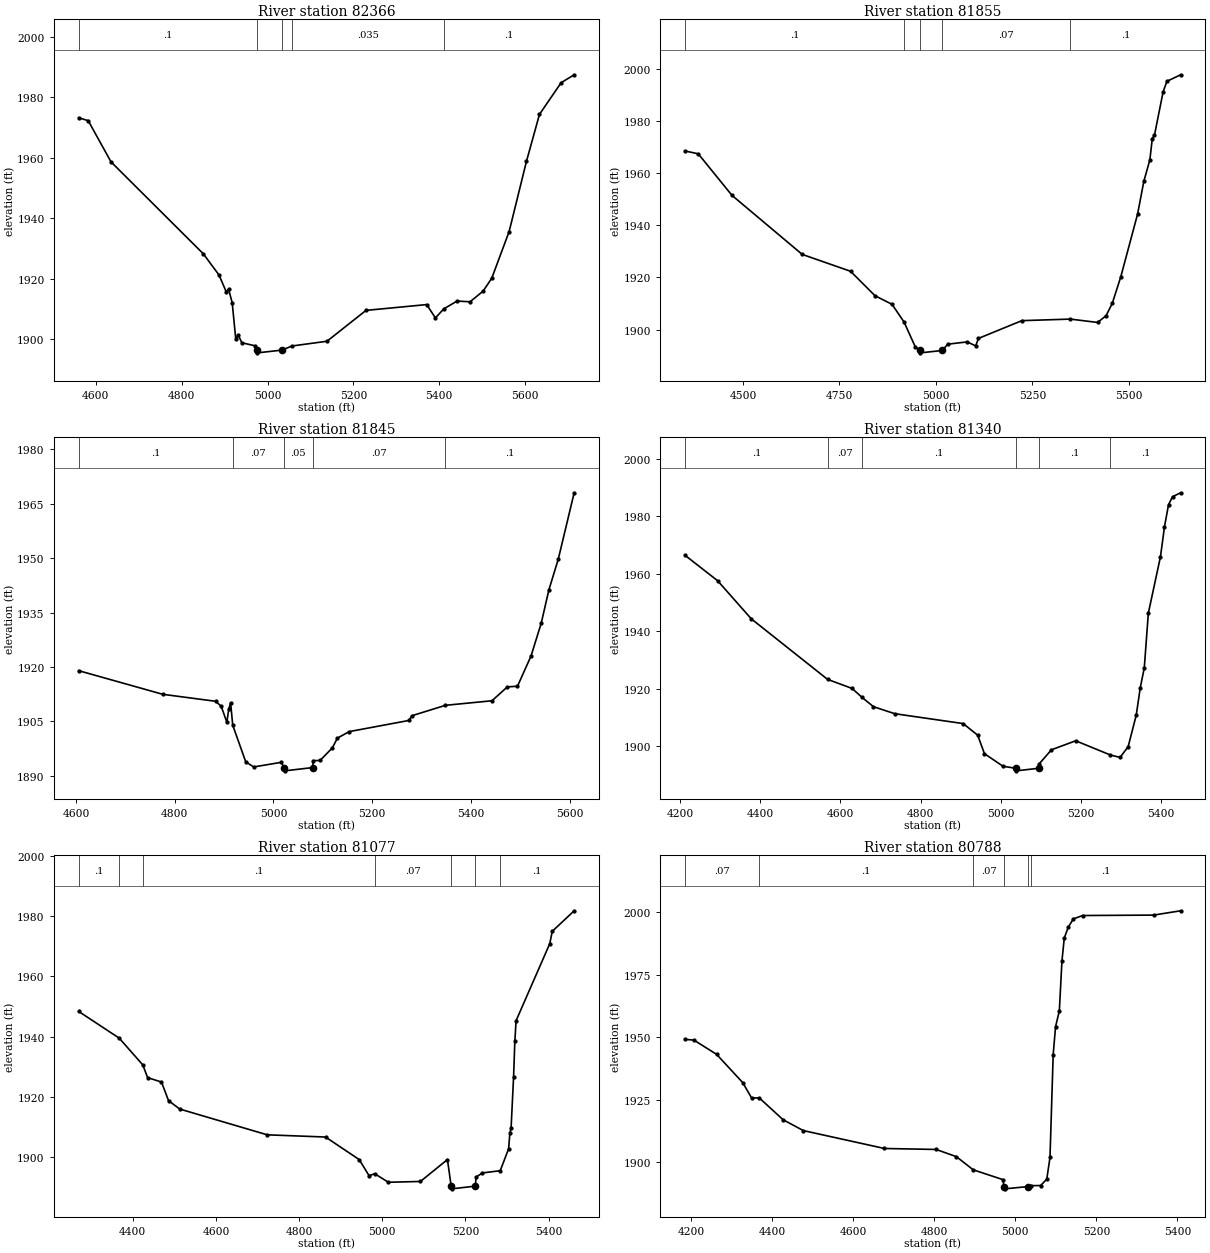
Type RM Length L Ch R = 1 ,82366   ,511,511,511
BEGIN DESCRIPTION:
Johnson Creek 99.0
END DESCRIPTION:
XS GIS Cut Line= 3
      1849074.96     13975124.98        1848675.       13974925.
      1847974.98       13974825.
#Sta/Elev= 30
    4560 1973.27  4582.3 1972.32  4635.4  1958.7  4850.6 1928.29    4887 1921.31
  4903.8 1915.76  4909.3 1916.61  4917.7 1912.17  4926.1 1900.02  4931.7 1901.51
  4940.1 1898.93  4970.8 1897.92  4975.2 1896.49  4976.6 1895.59  5033.5 1896.49
  5056.9 1897.85  5138.5 1899.42  5229.4 1909.62  5370.8 1911.54    5391 1907.13
  5410.5  1910.1  5441.5  1912.7  5471.8 1912.46  5502.1 1915.98  5522.3 1920.24
  5562.8 1935.67  5603.2  1958.9  5633.5 1974.41    5684 1984.87  5714.3 1987.48
#Mann= 5 ,-1 , 0
    4560      .1       0  4975.2     .05       0  5033.5      .1       0
  5056.9    .035       0  5410.5      .1       0
Bank Sta=4975.2,5033.5
XS Rating Curve= 0 ,0
Exp/Cntr=0.3,0.1

Type RM Length L Ch R = 1 ,81855   ,515,515,515
BEGIN DESCRIPTION:
Johnson Creek 98.0
END DESCRIPTION:
XS GIS Cut Line= 3
      1849224.99       13974575.        1848575.       13974475.
      1848025.03     13974175.02
#Sta/Elev= 30
  4350.2 1968.45  4384.3 1967.36  4471.6 1951.45  4653.7 1928.82  4778.9 1922.36
  4842.2    1913  4886.4  1909.7  4917.6 1902.91  4947.1 1893.26  4958.5 1892.01
  4959.9 1891.11  5016.8 1892.01  5030.6 1894.43  5081.4  1895.3  5103.2 1893.76
  5110.4 1896.64  5222.8 1903.44  5348.5 1904.04  5419.3 1902.75  5441.2 1905.37
  5457.3 1910.13  5479.1 1920.19  5522.8  1944.3  5538.9  1956.8  5554.6 1965.07
  5560.8 1973.21  5566.5 1974.51  5588.8 1991.04  5598.7 1995.14  5634.3 1997.64
#Mann= 5 ,-1 , 0
  4350.2      .1       0  4917.6     .07       0  4958.5     .05       0
  5016.8     .07       0  5348.5      .1       0
Bank Sta=4958.5,5016.8
XS Rating Curve= 0 ,0
Exp/Cntr=0.3,0.1

Type RM Length L Ch R = 1 ,81845   ,505,505,505
BEGIN DESCRIPTION:
Johnson Creek 98.0
END DESCRIPTION:
XS GIS Cut Line= 3
       1848895.6     13974222.89        1848575.       13974475.
      1848055.32     13974766.29
#Sta/Elev= 30
  4605.5 1918.99  4775.8 1912.48  4882.8 1910.56  4894.2  1909.2  4905.7 1904.77
  4909.5 1908.37  4913.3 1910.12  4917.6 1903.96  4943.9 1893.89    4960 1892.47
  5016.1 1893.75  5021.3  1892.3  5022.7  1891.4  5079.6  1892.3  5080.5  1894.2
  5094.5 1894.26  5119.3 1897.72  5129.6 1900.42  5153.7 1902.21  5274.1 1905.27
    5281  1906.6  5348.5 1909.45  5442.7  1910.7  5473.7 1914.52  5494.3  1914.7
  5521.8 1923.05  5542.5 1932.13  5557.9 1941.25  5576.9  1949.7  5609.1 1967.98
#Mann= 5 ,-1 , 0
  4605.5      .1       0  4917.6     .07       0  5021.3     .05       0
  5079.6     .07       0  5348.5      .1       0
Bank Sta=5021.3,5079.6
XS Rating Curve= 0 ,0
Exp/Cntr=0.3,0.1

Type RM Length L Ch R = 1 ,81340   ,552,552,552
BEGIN DESCRIPTION:
Johnson Creek 97.0
END DESCRIPTION:
XS GIS Cut Line= 3
        1849275.       13974375.        1848575.       13974025.
      1848124.99       13973975.
#Sta/Elev= 30
  4212.8 1966.41  4293.9 1957.58  4377.7 1944.34    4568 1923.27  4629.3 1920.11
  4653.4 1917.07  4682.4 1913.77  4735.5 1911.33    4906  1907.9  4942.3 1903.85
  4959.1 1897.42  5005.5 1893.05  5036.7 1892.36  5038.1 1891.46    5095 1892.36
    5096 1893.96  5126.2 1898.79  5186.6 1901.91  5273.3 1896.96  5297.3 1896.13
  5317.4 1899.89  5337.5 1910.83  5347.6  1920.4  5357.6 1927.32  5367.7 1946.33
  5397.9 1965.92  5407.9 1976.31    5418 1984.03  5428.1 1986.81  5448.2 1988.17
#Mann= 6 ,-1 , 0
  4212.8      .1       0    4568     .07       0  4653.4      .1       0
  5036.7     .05       0    5095      .1       0  5273.3      .1       0
Bank Sta=5036.7,5095
XS Rating Curve= 0 ,0
Exp/Cntr=0.3,0.1

Type RM Length L Ch R = 1 ,81077   ,289,289,289
BEGIN DESCRIPTION:
Johnson Creek 77.2
END DESCRIPTION:
XS GIS Cut Line= 5
      1849227.19     13974113.51      1848596.99      13973790.6
      1848557.06     13973795.81      1848428.59     13973828.79
      1848117.85       13973834.
#Sta/Elev= 30
  4269.9 1948.34  4367.4 1939.49  4424.3 1930.59  4435.8 1926.39  4469.2 1924.92
  4486.1 1918.75    4513 1915.97  4723.5 1907.42  4863.7 1906.69  4944.6 1899.22
  4968.3  1893.9  4982.3  1894.5  5014.7 1891.69    5092 1891.96  5156.9 1899.22
  5165.9 1890.41  5167.3 1889.51  5224.2 1890.41  5225.6 1893.39  5240.9 1894.78
  5283.9 1895.53    5304 1902.78    5307 1907.86    5310 1909.72    5316 1926.68
    5319 1938.37    5322 1945.27    5403 1970.81    5409  1974.9  5461.7 1981.71
#Mann= 7 ,-1 , 0
  4269.9      .1       0  4367.4     .07       0  4424.3      .1       0
  4982.3     .07       0  5165.9     .05       0  5224.2     .07       0
  5283.9      .1       0
Bank Sta=5165.9,5224.2
XS Rating Curve= 0 ,0
Exp/Cntr=0.3,0.1

Type RM Length L Ch R = 1 ,80788   ,557,557,557
BEGIN DESCRIPTION:
Johnson Creek 96.0
END DESCRIPTION:
XS GIS Cut Line= 3
      1849275.03     13974025.03        1848625.       13973525.
      1848425.01     13973175.01
#Sta/Elev= 30
  4184.9 1949.17  4206.7 1948.86  4262.8 1943.14  4327.2 1931.83    4349 1925.71
  4368.2 1925.69  4426.9 1916.96  4476.7 1912.63    4677 1905.46  4804.7 1905.07
  4854.6 1902.18  4896.1 1896.92  4968.7 1893.03  4972.6  1890.2    4974  1889.3
    5031  1890.2  5038.6 1890.57  5062.6 1890.63  5077.7 1893.22  5085.6 1901.85
  5093.5 1943.08  5099.3 1954.19  5108.7 1960.59  5115.1  1980.5  5120.9 1989.79
    5131 1994.17  5143.2 1997.39  5166.2 1998.75  5341.2 1998.92  5408.1 2000.65
#Mann= 6 ,-1 , 0
  4184.9     .07       0  4368.2      .1       0  4896.1     .07       0
  4972.6     .05       0    5031     .07       0  5038.6      .1       0
Bank Sta=4972.6,5031
XS Rating Curve= 0 ,0
Exp/Cntr=0.3,0.1

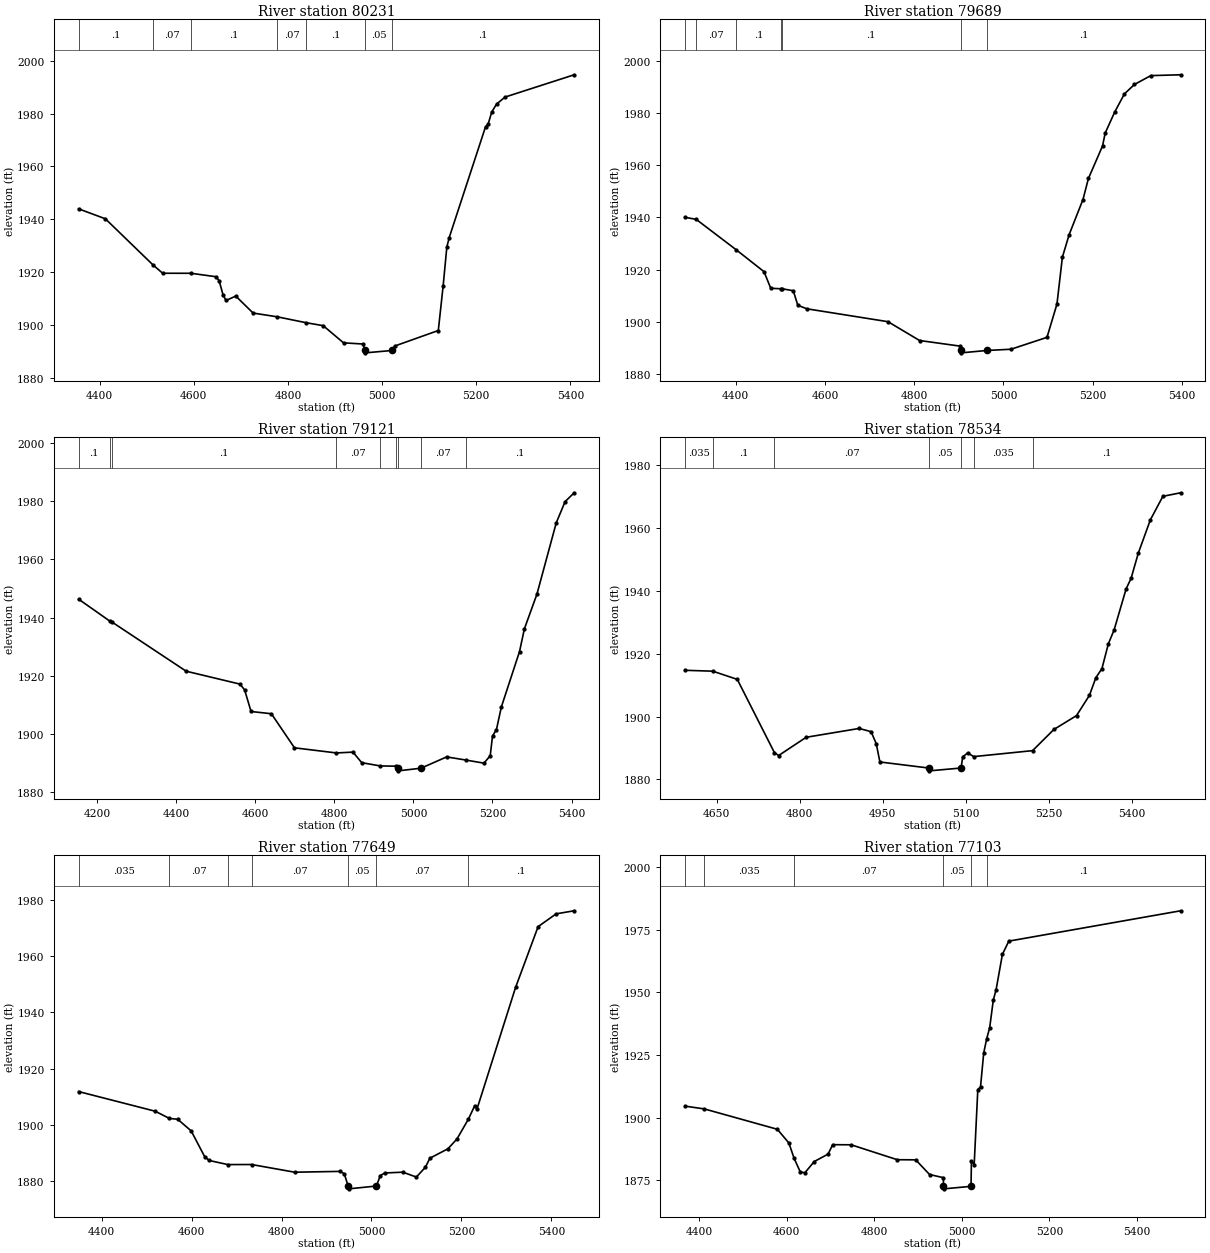
Type RM Length L Ch R = 1 ,80231   ,542,542,542
BEGIN DESCRIPTION:
Johnson Creek 95.0
END DESCRIPTION:
XS GIS Cut Line= 3
      1849475.01     13973725.01        1849075.       13973225.
      1848675.03     13973125.01
#Sta/Elev= 30
  4355.5 1943.98  4412.3 1940.21  4513.3 1922.79    4534 1919.61  4594.2  1919.6
  4647.7 1918.29  4654.1 1916.69  4662.1 1911.54  4668.5 1909.31  4689.3 1910.97
  4726.1 1904.55  4777.1 1903.14  4838.4 1900.91    4875 1899.78  4918.2 1893.28
  4959.8 1892.84  4963.4  1890.4  4964.8  1889.5  5021.8  1890.4  5026.7 1892.06
  5119.5 1897.95  5129.8 1914.87  5137.6  1929.5  5142.7 1933.13    5220 1975.12
  5225.2 1975.92  5232.9 1980.58  5243.2 1983.61  5261.2 1986.26  5408.1  1994.7
#Mann= 7 ,-1 , 0
  4355.5      .1       0  4513.3     .07       0  4594.2      .1       0
  4777.1     .07       0  4838.4      .1       0  4963.4     .05       0
  5021.8      .1       0
Bank Sta=4963.4,5021.8
XS Rating Curve= 0 ,0
Exp/Cntr=0.3,0.1

Type RM Length L Ch R = 1 ,79689   ,568,568,568
BEGIN DESCRIPTION:
Johnson Creek 94.0
END DESCRIPTION:
XS GIS Cut Line= 3
        1849525.       13973625.        1849425.       13972925.
      1849075.01     13972725.01
#Sta/Elev= 30
  4286.8 1939.99  4311.5 1939.25    4401 1927.63  4463.6 1919.21  4478.7 1912.84
  4500.8 1912.68  4503.3  1912.7  4529.2  1911.9  4539.3 1906.35  4559.5    1905
  4741.4 1900.06  4812.1 1892.86    4903 1890.71  4904.1 1889.04  4905.5 1888.14
  4962.5 1889.04  5016.9 1889.52  5097.6 1894.07  5119.9 1906.82  5132.1 1924.76
  5147.2 1933.39  5178.2 1946.82  5190.4 1954.88  5222.1 1967.36  5227.9 1972.25
  5249.4 1980.34    5271 1987.25  5293.4 1990.85  5330.1 1994.25    5397 1994.57
#Mann= 7 ,-1 , 0
  4286.8      .1       0  4311.5     .07       0    4401      .1       0
  4500.8     .07       0  4503.3      .1       0  4904.1     .05       0
  4962.5      .1       0
Bank Sta=4904.1,4962.5
XS Rating Curve= 0 ,0
Exp/Cntr=0.3,0.1

Type RM Length L Ch R = 1 ,79121   ,587,587,587
BEGIN DESCRIPTION:
Johnson Creek 93.0
END DESCRIPTION:
XS GIS Cut Line= 3
      1850275.02     13973475.03        1849875.       13972725.
      1849525.04     13972525.02
#Sta/Elev= 30
  4153.5 1946.36  4232.8 1938.79    4237 1938.58  4425.5 1921.61  4561.5 1917.18
  4573.2 1915.21  4589.5 1907.77  4640.9    1907  4699.3 1895.29  4805.3 1893.53
  4847.3 1893.81  4869.3 1890.19    4916 1889.07  4955.9 1888.98  4960.4 1888.28
  4961.8 1887.38  5019.1 1888.28  5084.2 1892.17  5132.1  1891.1  5178.5 1890.02
  5194.3 1892.57  5200.1 1899.34  5210.1 1901.57  5222.4  1909.3  5268.4 1928.36
  5280.7 1936.17  5312.3 1948.03  5361.3  1972.6  5383.6 1979.87  5406.6 1982.92
#Mann= 9 ,-1 , 0
  4153.5      .1       0  4232.8     .07       0    4237      .1       0
  4805.3     .07       0    4916      .1       0  4955.9     .07       0
  4960.4     .05       0  5019.1     .07       0  5132.1      .1       0
Bank Sta=4960.4,5019.1
XS Rating Curve= 0 ,0
Exp/Cntr=0.3,0.1

Type RM Length L Ch R = 1 ,78534   ,885,885,885
BEGIN DESCRIPTION:
Johnson Creek 92.0
END DESCRIPTION:
XS GIS Cut Line= 3
      1850524.99     13972824.98        1850325.       13972475.
      1849875.03     13972275.01
#Sta/Elev= 30
  4592.6 1914.71  4642.6 1914.43  4686.9 1911.82    4754 1888.51  4761.7 1887.59
  4811.4 1893.39  4907.1  1896.2  4928.7 1895.18  4938.1 1891.31  4944.6 1885.53
  5032.7 1883.61  5034.1 1882.71  5091.4 1883.61  5094.2 1887.15  5103.1 1888.39
  5114.3 1887.24  5220.6 1889.14    5259 1895.87    5300  1900.3  5323.3 1906.75
  5334.9 1912.35  5345.9 1915.27  5357.5 1923.16  5367.8 1927.51  5389.6 1940.64
  5398.5 1943.95  5411.5 1951.95  5433.4  1962.6    5456 1970.08  5488.1 1971.21
#Mann= 7 ,-1 , 0
  4592.6    .035       0  4642.6      .1       0    4754     .07       0
  5032.7     .05       0  5091.4     .07       0  5114.3    .035       0
  5220.6      .1       0
Bank Sta=5032.7,5091.4
XS Rating Curve= 0 ,0
Exp/Cntr=0.3,0.1

Type RM Length L Ch R = 1 ,77649   ,546,546,546
BEGIN DESCRIPTION:
Johnson Creek 91.0
END DESCRIPTION:
XS GIS Cut Line= 3
        1850925.     13972624.95      1850956.16      13971973.7
        1850925.     13971524.98
#Sta/Elev= 30
  4348.9 1911.85    4519 1904.87  4550.8  1902.3  4569.1 1902.01  4599.1 1897.88
  4629.2 1888.69  4639.2 1887.36  4680.6  1885.9  4733.6 1885.92  4829.4 1883.19
  4929.5 1883.48  4939.5 1882.68  4948.1 1878.28  4949.6 1877.28  5011.1 1878.28
  5019.6    1882  5029.7 1882.92  5069.8  1883.2  5099.8 1881.46  5119.9 1884.96
  5129.9 1888.17    5170 1891.51  5190.1    1895  5215.5 1902.04  5229.6 1906.85
  5234.7 1905.68  5320.4 1948.85  5370.5 1970.46  5410.6 1975.01  5450.7  1976.1
#Mann= 7 ,-1 , 0
  4348.9    .035       0  4550.8     .07       0  4680.6    .035       0
  4733.6     .07       0  4948.1     .05       0  5011.1     .07       0
  5215.5      .1       0
Bank Sta=4948.1,5011.1
XS Rating Curve= 0 ,0
Exp/Cntr=0.3,0.1

Type RM Length L Ch R = 1 ,77103   ,690,690,690
BEGIN DESCRIPTION:
Johnson Creek 90.0
END DESCRIPTION:
XS GIS Cut Line= 3
      1851225.01     13972524.98        1851425.       13971925.
      1851724.98     13971525.03
#Sta/Elev= 30
  4367.5 1904.65  4411.6 1903.53  4578.3 1895.41  4604.7 1889.94  4616.5 1883.87
    4631 1878.28  4641.5 1878.12  4662.6 1882.54  4694.2  1885.5  4704.8 1889.27
    4747 1889.22  4852.4 1883.27  4894.5 1883.22  4926.1 1877.37  4957.8  1876.1
  4957.9 1872.65  4959.4 1871.65  5020.9 1872.65  5021.8 1882.76  5028.1 1881.27
  5036.4 1911.26  5042.6 1912.35  5049.9 1925.86  5056.7 1931.56  5063.5  1935.9
  5071.8 1946.96  5078.1 1951.03  5092.6 1965.18  5107.2 1970.48  5499.9 1982.59
#Mann= 6 ,-1 , 0
  4367.5      .1       0  4411.6    .035       0  4616.5     .07       0
  4957.9     .05       0  5020.9     .07       0  5056.7      .1       0
Bank Sta=4957.9,5020.9
XS Rating Curve= 0 ,0
Exp/Cntr=0.3,0.1

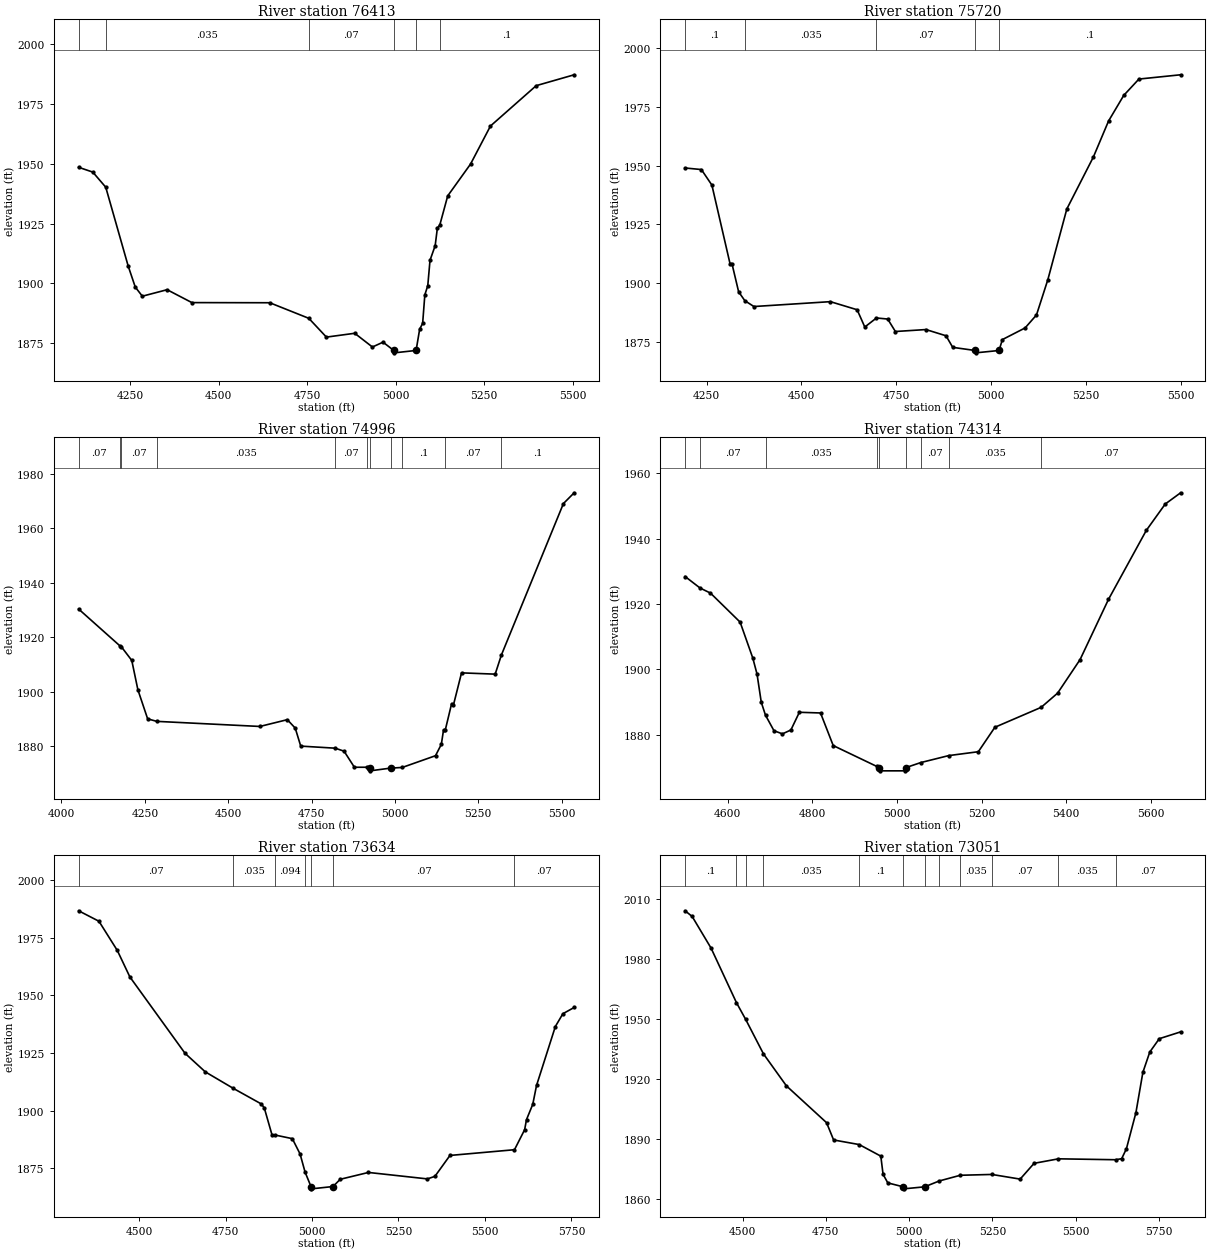
Type RM Length L Ch R = 1 ,76413   ,693,693,693
BEGIN DESCRIPTION:
Johnson Creek 89.0
END DESCRIPTION:
XS GIS Cut Line= 3
        1852025.     13973074.98        1852025.       13972175.
      1852425.02     13971874.99
#Sta/Elev= 30
  4104.3 1948.55  4144.3 1946.54  4180.9 1940.21  4244.3 1907.19  4264.3 1898.39
  4284.3 1894.56  4354.3 1897.28  4424.3 1891.88  4644.3 1891.82  4754.6  1885.3
  4804.3 1877.43  4884.3 1879.03  4934.3 1873.28  4964.3 1875.31  4994.6 1871.84
  4996.1 1870.84  5057.7 1871.84  5067.8 1880.76  5076.2 1883.17  5082.4 1895.15
  5090.7 1898.96    5097  1909.6  5111.6 1915.73  5117.8 1923.09  5124.6 1924.34
    5147 1936.57  5211.6 1949.92  5267.8 1965.84    5397 1982.74  5504.3  1987.3
#Mann= 6 ,-1 , 0
  4104.3     .07       0  4180.9    .035       0  4754.6     .07       0
  4994.6     .05       0  5057.7     .07       0  5124.6      .1       0
Bank Sta=4994.6,5057.7
XS Rating Curve= 0 ,0
Exp/Cntr=0.3,0.1

Type RM Length L Ch R = 1 ,75720   ,724,724,724
BEGIN DESCRIPTION:
Johnson Creek 88.0
END DESCRIPTION:
XS GIS Cut Line= 3
        1852525.     13973075.03        1852625.       13972275.
        1852625.     13971774.95
#Sta/Elev= 30
  4193.4 1948.98  4236.3 1948.32    4264 1941.73  4311.8 1908.36  4316.9 1908.37
  4334.5  1896.4  4350.9 1892.61  4374.8 1890.14  4576.4 1892.21  4646.9 1888.77
  4667.1 1881.43  4697.9 1885.28  4727.5 1884.82  4747.7 1879.53  4828.3 1880.36
  4881.2 1877.72  4898.9  1872.8    4958 1871.47  4959.5 1870.47  5021.1 1871.47
  5029.7 1876.09  5089.7 1881.05  5119.7 1886.56  5149.7 1901.58  5199.7 1931.58
  5269.7 1953.66  5309.7 1968.94  5349.7 1979.81  5389.7 1986.75  5499.7 1988.57
#Mann= 5 ,-1 , 0
  4193.4      .1       0  4350.9    .035       0  4697.9     .07       0
    4958     .05       0  5021.1      .1       0
Bank Sta=4958,5021.1
XS Rating Curve= 0 ,0
Exp/Cntr=0.3,0.1

Type RM Length L Ch R = 1 ,74996   ,682,682,682
BEGIN DESCRIPTION:
Johnson Creek 87.0
END DESCRIPTION:
XS GIS Cut Line= 3
      1852909.73     13973149.86        1853275.       13972275.
      1853074.99     13971774.97
#Sta/Elev= 30
  4051.4 1930.29  4175.3 1916.78  4179.7 1916.43  4210.8 1911.45  4229.2 1900.66
  4258.4 1890.02  4285.7 1889.09  4595.1 1887.22  4677.4 1889.71  4701.2 1886.61
  4717.7 1880.01  4821.2 1879.25  4847.7 1878.15  4878.7 1872.25  4916.6 1872.26
  4924.1 1871.94  4925.6 1870.94  4987.2 1871.94  5022.2 1872.18    5122 1876.49
  5139.5 1880.66  5146.2 1886.03  5151.1 1885.79  5170.4 1895.62  5175.8 1895.08
  5200.1 1906.88    5301 1906.41  5319.8 1913.47  5505.7 1968.98    5538 1972.94
#Mann= 11 ,-1 , 0
  4051.4     .07       0  4175.3    .035       0  4179.7     .07       0
  4285.7    .035       0  4821.2     .07       0  4916.6     .07       0
  4924.1     .05       0  4987.2     .07       0  5022.2      .1       0
  5151.1     .07       0  5319.8      .1       0
Bank Sta=4924.1,4987.2
XS Rating Curve= 0 ,0
Exp/Cntr=0.3,0.1

Type RM Length L Ch R = 1 ,74314   ,680,680,680
BEGIN DESCRIPTION:
Johnson Creek 86.0
END DESCRIPTION:
XS GIS Cut Line= 3
        1853875.     13972725.05        1853875.       13972225.
      1853574.99     13971624.97
#Sta/Elev= 30
  4499.5 1928.44  4534.7 1924.93  4559.5 1923.36  4629.5 1914.49  4659.5 1903.48
  4669.5 1898.58  4679.5 1889.96  4689.5 1886.01  4709.5 1881.27  4729.5 1880.31
  4749.5  1881.5  4769.5 1886.91  4819.5  1886.7  4849.5 1876.73  4952.3 1870.36
  4957.7    1870  4959.2    1869  5019.9    1869  5021.4    1870  5056.4 1871.53
  5122.3 1873.66  5192.4 1874.85  5231.5 1882.33  5340.8 1888.42  5379.7 1892.77
  5432.8 1903.03  5499.9 1921.44  5589.3 1942.55    5634 1950.61  5670.4 1954.05
#Mann= 9 ,-1 , 0
  4499.5    .035       0  4534.7     .07       0  4689.5    .035       0
  4952.3     .07       0  4957.7     .05       0  5021.4     .07       0
  5056.4     .07       0  5122.3    .035       0  5340.8     .07       0
Bank Sta=4957.7,5021.4
XS Rating Curve= 0 ,0
Exp/Cntr=0.3,0.1

Type RM Length L Ch R = 1 ,73634   ,583,583,583
BEGIN DESCRIPTION:
Johnson Creek 85.0
END DESCRIPTION:
XS GIS Cut Line= 3
        1854775.     13972775.01        1854475.       13972175.
        1854175.     13971475.01
#Sta/Elev= 30
  4325.4 1986.65  4384.1 1982.11  4437.2 1969.44  4473.5 1957.96  4632.9 1924.84
  4691.6 1916.77  4772.7  1909.6  4853.7 1902.84  4862.1 1901.11  4884.4 1889.43
  4894.1 1889.35  4943.1 1887.81  4965.5 1881.16  4979.9 1873.33    4997 1867.04
  4998.5 1866.04  5060.7 1867.04  5081.5 1870.18  5163.1 1873.15  5333.5 1870.35
  5355.3 1871.46  5398.8 1880.53  5585.3 1883.01  5614.6 1891.68    5620 1896.07
  5638.1 1902.69    5649 1910.88  5703.4 1936.45  5725.2    1942  5757.8 1944.71
#Mann= 7 ,-1 , 0
  4325.4     .07       0  4772.7    .035       0  4894.1    .094       0
  4979.9     .07       0    4997     .05       0  5060.7     .07       0
  5585.3     .07       0
Bank Sta=4997,5060.7
XS Rating Curve= 0 ,0
Exp/Cntr=0.3,0.1

Type RM Length L Ch R = 1 ,73051   ,785,785,785
BEGIN DESCRIPTION:
Johnson Creek 84.0
END DESCRIPTION:
XS GIS Cut Line= 3
      1855424.99     13972374.99      1854949.25     13971924.75
      1854325.02     13971375.02
#Sta/Elev= 30
  4327.7 2004.09  4348.9 2001.24  4405.6 1985.44  4481.8 1958.18  4509.3 1949.86
  4562.9 1932.57  4631.7  1916.6  4752.2  1898.2  4773.3 1889.57  4850.2 1887.27
  4914.9 1881.49  4921.7  1872.4  4935.9 1868.12  4982.4 1866.15  4983.9 1865.15
  5046.2 1866.15  5090.5  1869.1  5153.4 1871.93  5248.1 1872.34    5333 1870.01
  5374.8  1877.9    5448 1880.15  5619.8 1879.69  5637.6 1880.23  5651.8 1885.17
  5680.3 1903.19  5701.2 1923.37    5722 1933.53  5750.5 1940.18  5814.5 1943.58
#Mann= 12 ,-1 , 0
  4327.7      .1       0  4481.8     .07       0  4509.3      .1       0
  4562.9    .035       0  4850.2      .1       0  4982.4     .05       0
  5046.2      .1       0  5090.5     .07       0  5153.4    .035       0
  5248.1     .07       0    5448    .035       0  5619.8     .07       0
Bank Sta=4982.4,5046.2
XS Rating Curve= 0 ,0
Exp/Cntr=0.3,0.1