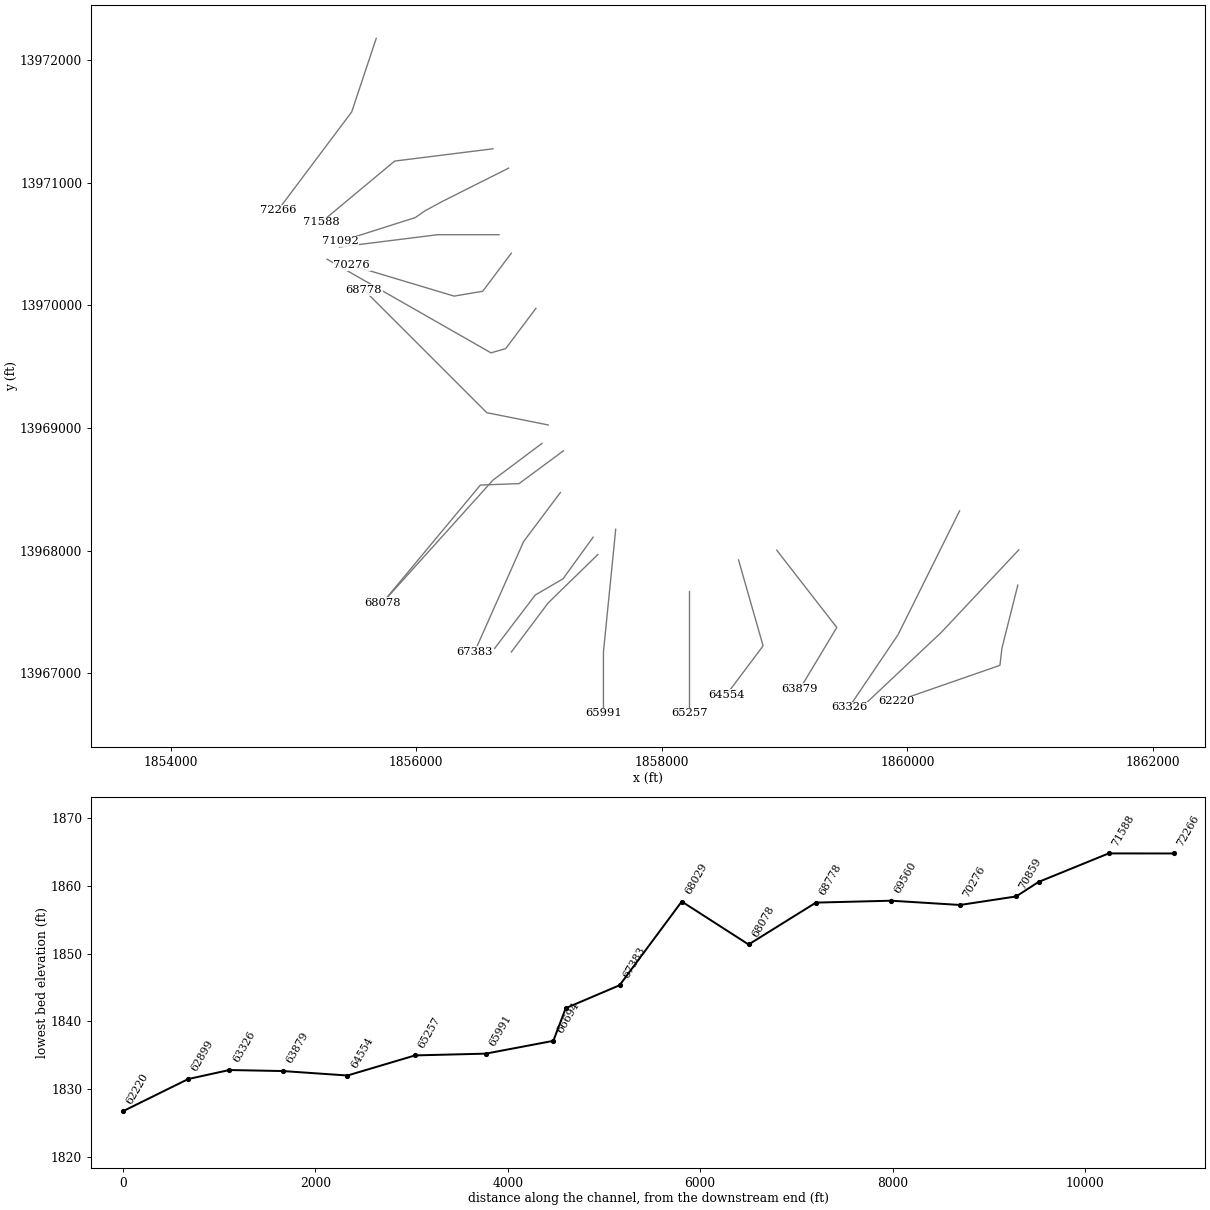
HEC-RAS study Johnson Creek.prj: Johnson Creek Base Level Engineering

--- Johnson Creek.g01 (geometry) --- (continued)

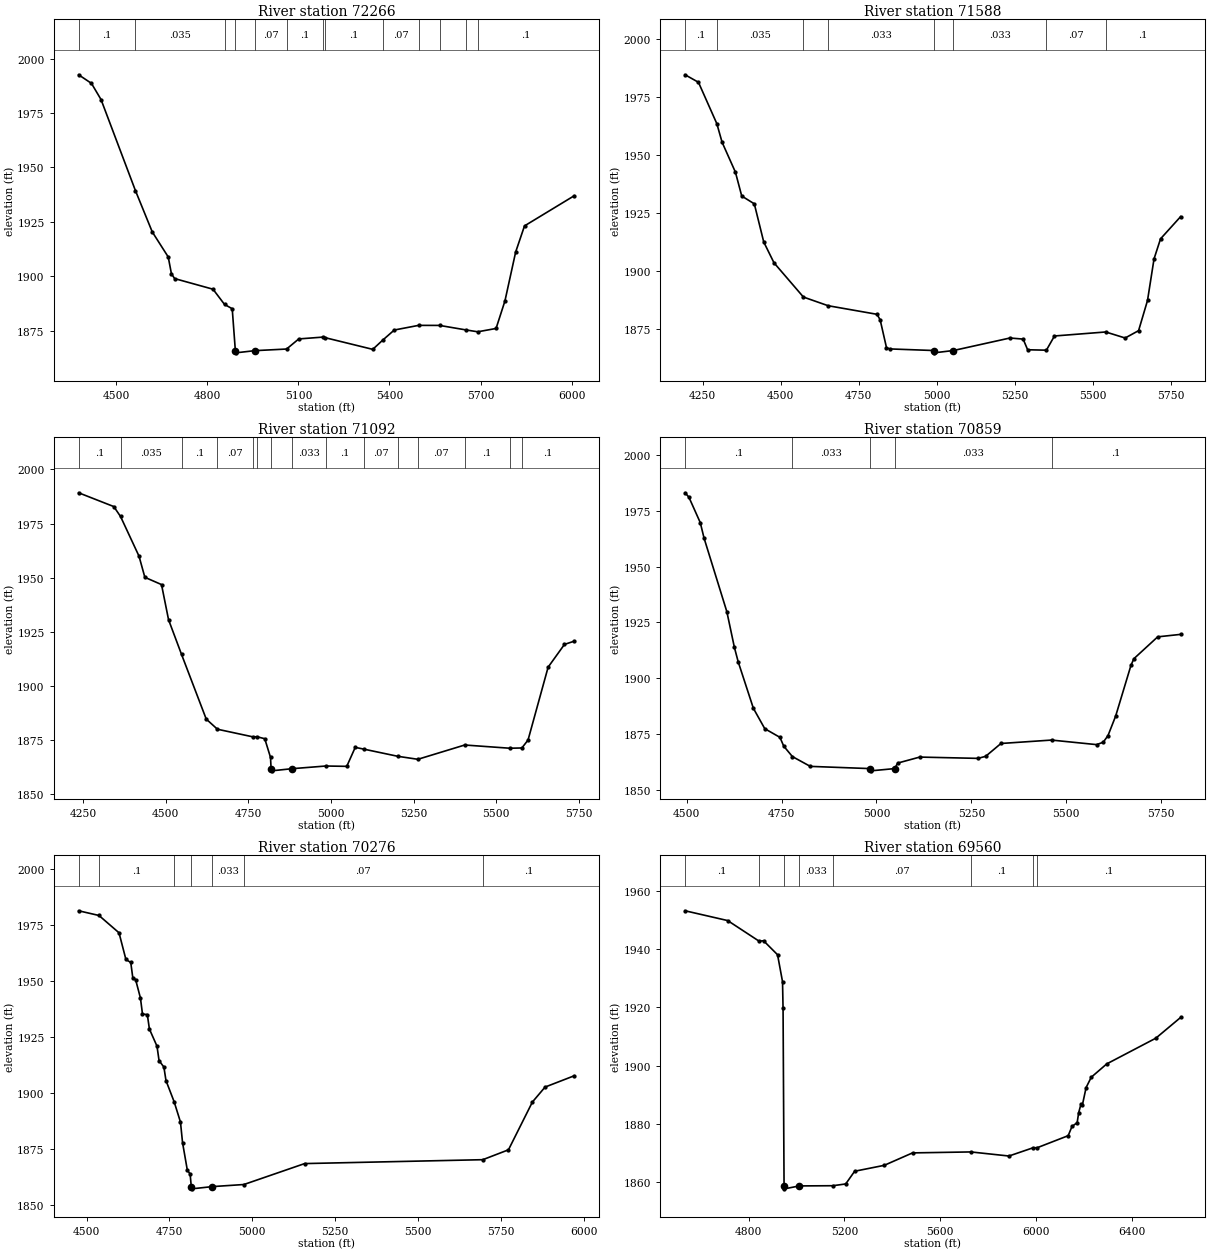
Type RM Length L Ch R = 1 ,72266   ,678,678,678
BEGIN DESCRIPTION:
Johnson Creek 83.0
END DESCRIPTION:
XS GIS Cut Line= 3
      1855675.01     13972175.03        1855475.       13971575.
      1854874.99     13970774.99
#Sta/Elev= 30
    4376 1992.54  4418.2  1988.6  4449.8 1981.16    4563 1939.37  4618.5 1920.36
  4671.2 1908.84  4681.7 1901.11  4692.3  1898.9  4818.7 1894.02  4856.6 1887.04
    4882 1885.05  4892.3 1865.79  4893.8 1864.79  4956.1 1865.79  5061.1 1866.54
  5101.2 1871.18  5180.8 1872.02  5187.1 1871.79  5344.9 1866.39  5378.1 1870.66
  5415.8 1875.27    5496 1877.41    5565 1877.39  5653.5 1875.28  5690.9 1874.46
  5751.2 1875.99  5780.4 1888.62  5815.8 1911.14  5844.9 1923.11  6008.5 1936.95
#Mann= 13 ,-1 , 0
    4376      .1       0    4563    .035       0  4856.6     .07       0
  4892.3    .033       0  4956.1     .07       0  5061.1      .1       0
  5180.8     .07       0  5187.1      .1       0  5378.1     .07       0
    5496    .035       0    5565     .07       0  5653.5    .035       0
  5690.9      .1       0
Bank Sta=4892.3,4956.1
XS Rating Curve= 0 ,0
Exp/Cntr=0.3,0.1

Type RM Length L Ch R = 1 ,71588   ,729,729,729
BEGIN DESCRIPTION:
Johnson Creek 82.0
END DESCRIPTION:
XS GIS Cut Line= 3
      1856624.98       13971275.        1855825.       13971175.
      1855225.02     13970675.02
#Sta/Elev= 30
  4194.1 1984.59  4236.9 1981.35  4295.8 1963.51  4312.5 1955.55  4355.3 1942.63
  4375.5 1932.36  4415.8 1928.99    4446 1912.55  4478.8 1903.59  4573.1 1888.83
  4652.2  1885.1  4808.8  1881.4  4818.9 1879.01  4839.1 1867.07  4849.1 1866.49
  4989.9  1865.8  4991.4  1864.8  5053.7  1865.8  5234.6 1871.19  5276.9 1870.72
  5291.2 1866.13  5351.3 1865.94  5377.2 1872.06  5541.3 1873.79  5603.6 1871.19
  5646.6 1874.36  5675.2 1887.36  5696.1 1905.29  5716.9 1913.91  5781.3 1923.49
#Mann= 8 ,-1 , 0
  4194.1      .1       0  4295.8    .035       0  4573.1     .07       0
  4652.2    .033       0  4989.9    .033       0  5053.7    .033       0
  5351.3     .07       0  5541.3      .1       0
Bank Sta=4989.9,5053.7
XS Rating Curve= 0 ,0
Exp/Cntr=0.3,0.1

Type RM Length L Ch R = 1 ,71092   ,233,233,233
BEGIN DESCRIPTION:
Johnson Creek 77.1
END DESCRIPTION:
XS GIS Cut Line= 5
      1856752.66     13971117.28      1856218.85     13970849.07
      1856071.71     13970769.64      1855993.59     13970714.95
       1855384.2     13970520.94
#Sta/Elev= 30
  4236.3 1989.22  4342.7 1982.84  4363.1 1978.25    4419  1959.9  4436.7 1950.11
  4487.1 1946.75  4508.4 1930.49  4547.7 1914.44  4622.4 1884.53  4656.3 1879.83
  4764.9 1876.26  4775.7 1876.37  4799.5 1875.44  4816.9 1866.81  4818.7 1861.58
  4820.2 1860.58  4882.6 1861.58  4984.2 1862.81  5047.7 1862.66  5073.3 1871.44
  5100.2 1870.59  5202.6 1867.29  5262.8 1865.92  5404.6 1872.53  5540.8 1871.04
  5577.5 1871.16  5596.2 1874.82    5657 1908.55  5706.4 1919.07  5735.8 1920.56
#Mann= 15 ,-1 , 0
  4236.3      .1       0  4363.1    .035       0  4547.7      .1       0
  4656.3     .07       0  4764.9      .1       0  4775.7    .033       0
  4818.7     .05       0  4882.6    .033       0  4984.2      .1       0
  5100.2     .07       0  5202.6      .1       0  5262.8     .07       0
  5404.6      .1       0  5540.8     .07       0  5577.5      .1       0
Bank Sta=4818.7,4882.6
XS Rating Curve= 0 ,0
Exp/Cntr=0.3,0.1

Type RM Length L Ch R = 1 ,70859   ,583,583,583
BEGIN DESCRIPTION:
Johnson Creek 81.0
END DESCRIPTION:
XS GIS Cut Line= 3
      1856674.99       13970575.        1856175.       13970575.
      1855375.02       13970475.
#Sta/Elev= 30
  4495.5 1983.16  4505.5 1981.19  4535.5 1969.77  4545.5 1962.81  4605.5 1929.85
  4625.5 1913.78  4635.5 1907.32  4675.5 1886.48  4705.5 1877.35  4745.5 1873.46
  4755.5 1869.52  4778.3 1864.84  4825.5 1860.44  4983.7 1859.44  4985.2 1858.44
  5047.6 1859.44    5056 1861.93  5113.9 1864.61  5267.6 1864.03  5287.7 1864.95
  5328.1 1870.71  5461.4 1872.24    5580  1870.2  5597.6 1871.26  5610.2 1874.24
  5630.4    1883  5670.7 1905.72  5678.3 1908.71  5741.2 1918.54  5801.7 1919.65
#Mann= 5 ,-1 , 0
  4495.5      .1       0  4778.3    .033       0  4983.7    .033       0
  5047.6    .033       0  5461.4      .1       0
Bank Sta=4983.7,5047.6
XS Rating Curve= 0 ,0
Exp/Cntr=0.3,0.1

Type RM Length L Ch R = 1 ,70276   ,716,716,716
BEGIN DESCRIPTION:
Johnson Creek 80.0
END DESCRIPTION:
XS GIS Cut Line= 4
      1856775.01     13970425.01      1856541.95     13970114.27
      1856309.06     13970074.78      1855475.03     13970324.99
#Sta/Elev= 30
  4475.8 1981.38  4537.2 1979.28  4597.7 1971.54  4618.5 1959.62  4633.1 1958.29
  4639.4 1951.31  4647.7 1950.65  4662.3 1942.43  4668.5 1935.25  4683.1 1935.01
  4689.4 1928.55  4712.3 1920.89  4718.5 1914.45  4733.1 1911.57  4739.4 1905.54
    4764 1896.08  4783.1 1887.02  4789.4 1877.81  4803.9 1865.45  4812.3 1863.82
  4815.7 1858.18  4817.2 1857.18  4879.6 1858.18  4974.5 1859.11  5157.8 1868.46
  5695.5  1870.2  5772.9 1874.61  5845.1 1895.95  5883.4 1902.64  5971.2 1907.67
#Mann= 7 ,-1 , 0
  4475.8    .063       0  4537.2      .1       0    4764    .033       0
  4815.7    .033       0  4879.6    .033       0  4974.5     .07       0
  5695.5      .1       0
Bank Sta=4815.7,4879.6
XS Rating Curve= 0 ,0
Exp/Cntr=0.3,0.1

Type RM Length L Ch R = 1 ,69560   ,782,782,782
BEGIN DESCRIPTION:
Johnson Creek 79.0
END DESCRIPTION:
XS GIS Cut Line= 4
      1856975.01     13969975.02      1856728.63     13969646.51
      1856609.29     13969612.55      1855274.99     13970375.01
#Sta/Elev= 30
  4533.7 1953.12  4711.8 1949.76  4842.7 1942.72  4861.8 1942.84  4920.2 1938.05
    4941 1928.81  4943.2 1919.64  4947.4 1858.81  4948.9 1857.81  5011.3 1858.81
  5151.6 1858.88  5205.1 1859.49  5242.5 1863.84  5366.3 1865.87  5484.4 1870.13
    5728 1870.46  5887.5 1869.06  5987.9 1871.87  6005.8 1871.91  6135.1 1876.03
    6151 1879.19  6172.6 1880.49    6179 1883.93  6188.4 1886.79  6194.2 1886.44
    6210 1892.52  6231.6 1896.07  6296.4 1900.64  6501.5 1909.45  6605.2 1916.56
#Mann= 8 ,-1 , 0
  4533.7      .1       0  4842.7    .033       0  4947.4    .033       0
  5011.3    .033       0  5151.6     .07       0    5728      .1       0
  5987.9     .07       0  6005.8      .1       0
Bank Sta=4947.4,5011.3
XS Rating Curve= 0 ,0
Exp/Cntr=0.3,0.1

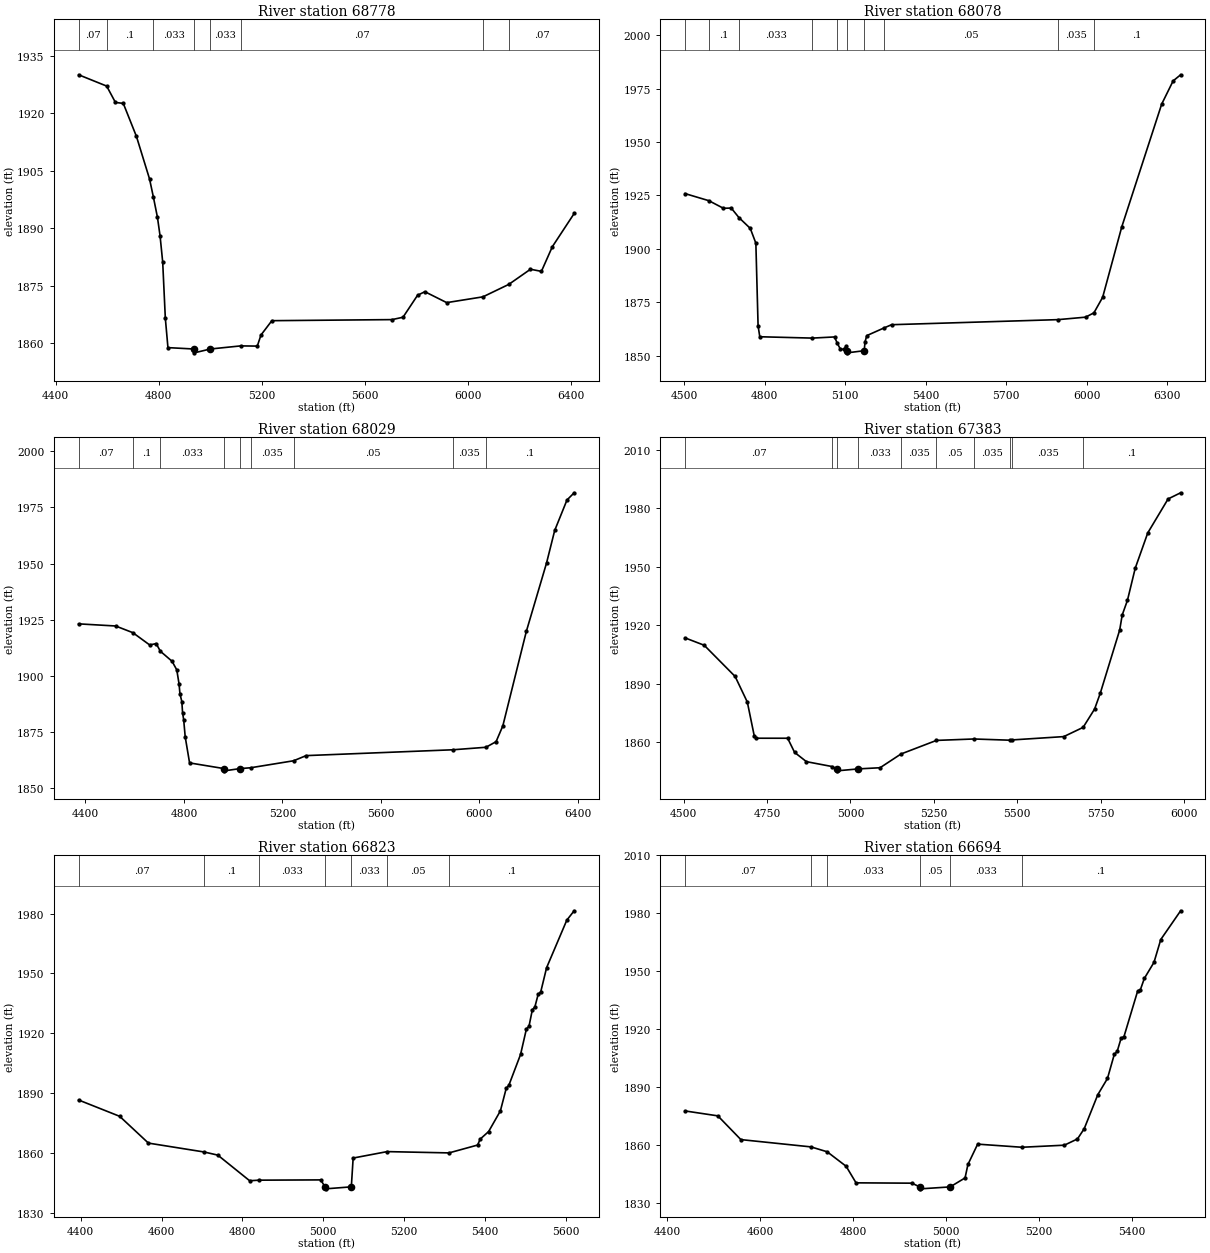
Type RM Length L Ch R = 1 ,68778   ,700,700,700
BEGIN DESCRIPTION:
Johnson Creek 78.0
END DESCRIPTION:
XS GIS Cut Line= 3
      1857075.02       13969025.        1856575.       13969125.
      1855575.02     13970124.98
#Sta/Elev= 30
  4489.7 1930.08  4598.6 1927.13  4632.5 1922.87  4663.1 1922.61  4714.1 1914.01
  4765.1 1902.88  4779.9 1898.19  4795.7  1892.9  4805.9 1888.05  4816.1 1881.23
  4826.3 1866.59  4836.5 1858.89  4937.1 1858.53  4938.6 1857.53    5001 1858.53
  5118.7 1859.34  5183.5 1859.29  5197.6 1862.17    5240 1865.92  5706.7  1866.2
  5749.2 1866.82  5805.7 1872.55    5834 1873.48  5918.9 1870.63  6059.5 1872.14
  6159.7 1875.38  6244.1 1879.34  6286.6 1878.79    6329 1885.22  6413.8 1893.89
#Mann= 8 ,-1 , 0
  4489.7     .07       0  4598.6      .1       0  4779.9    .033       0
  4937.1    .033       0    5001    .033       0  5118.7     .07       0
  6059.5      .1       0  6159.7     .07       0
Bank Sta=4937.1,5001
XS Rating Curve= 0 ,0
Exp/Cntr=0.3,0.1

Type RM Length L Ch R = 1 ,68078   ,695,695,695
BEGIN DESCRIPTION:
Johnson Creek 77.0
END DESCRIPTION:
XS GIS Cut Line= 3
      1857024.97     13968874.97        1856625.       13968575.
      1855725.01     13967575.02
#Sta/Elev= 30
    4504 1925.87  4592.6 1922.55  4646.7    1919  4675.8 1919.11  4704.4 1914.66
  4746.7 1909.59  4767.5 1902.66  4775.8 1863.98  4782.1 1858.87  4977.6 1858.24
  5060.4 1858.78  5070.9 1855.78  5082.1 1853.11  5096.3 1852.93    5103 1854.57
  5105.9 1852.34  5107.4 1851.34    5171 1852.34    5174 1856.48  5180.7 1859.41
  5245.2 1863.02    5273 1864.51  5892.7 1866.88  5995.4 1868.04  6026.4 1870.07
  6058.9 1877.34    6130 1910.27  6278.7 1967.76  6321.3 1978.62  6349.3 1981.49
#Mann= 10 ,-1 , 0
    4504     .07       0  4592.6      .1       0  4704.4    .033       0
  4977.6     .07       0  5070.9    .035       0  5105.9    .033       0
    5171    .035       0  5245.2     .05       0  5892.7    .035       0
  6026.4      .1       0
Bank Sta=5105.9,5171
XS Rating Curve= 0 ,0
Exp/Cntr=0.3,0.1

Type RM Length L Ch R = 1 ,68029   ,646,646,646
BEGIN DESCRIPTION:
Johnson Creek 77.0
END DESCRIPTION:
XS GIS Cut Line= 4
      1857198.76      13968813.9       1856838.1     13968546.99
      1856522.99     13968535.27      1855724.98     13967574.98
#Sta/Elev= 30
  4372.3 1923.13  4522.6 1922.18  4592.6  1919.2  4660.8 1913.74  4687.2 1914.34
  4704.4 1910.92  4751.6 1906.49  4770.9 1902.65  4780.2 1896.37  4783.8 1891.97
  4791.4 1888.56  4794.5 1883.52  4798.9 1880.48  4805.2 1872.78  4822.9 1861.22
  4962.9 1858.69  4964.4 1857.69    5028 1858.69  5070.9 1859.06  5245.2 1862.17
  5296.4 1864.47  5892.7 1867.07  6026.4 1868.18  6067.7 1870.67  6095.1 1877.69
  6190.5 1919.73  6272.6 1950.18  6305.8 1964.71  6355.7 1978.28  6384.9 1981.49
#Mann= 9 ,-1 , 0
  4372.3     .07       0  4592.6      .1       0  4704.4    .033       0
  4962.9     .05       0    5028    .033       0  5070.9    .035       0
  5245.2     .05       0  5892.7    .035       0  6026.4      .1       0
Bank Sta=4962.9,5028
XS Rating Curve= 0 ,0
Exp/Cntr=0.3,0.1

Type RM Length L Ch R = 1 ,67383   ,560,560,560
BEGIN DESCRIPTION:
Johnson Creek 76.0
END DESCRIPTION:
XS GIS Cut Line= 3
      1857175.01     13968475.02        1856875.       13968075.
        1856475.     13967175.01
#Sta/Elev= 30
  4504.5 1913.55  4561.8 1909.77  4654.5 1893.74    4691  1880.6  4711.8  1863.2
  4718.1 1862.06  4811.8 1862.05  4832.6 1854.79  4868.1 1850.03  4945.2 1847.52
  4958.4 1846.32  4959.9 1845.32  5023.6 1846.32  5088.7 1846.91  5151.4 1853.96
  5257.7 1860.94  5369.7 1861.67  5478.9 1861.04    5484 1861.18  5639.2 1862.89
  5697.2 1867.63  5731.6 1877.04  5748.7 1885.21  5806.8 1917.62  5814.3 1925.29
    5830 1932.83  5853.3  1949.3  5890.9 1967.44  5951.8 1984.87  5989.4 1988.03
#Mann= 10 ,-1 , 0
  4504.5     .07       0  4945.2    .033       0  4958.4    .033       0
  5023.6    .033       0  5151.4    .035       0  5257.7     .05       0
  5369.7    .035       0  5478.9     .05       0    5484    .035       0
  5697.2      .1       0
Bank Sta=4958.4,5023.6
XS Rating Curve= 0 ,0
Exp/Cntr=0.3,0.1

Type RM Length L Ch R = 1 ,66823   ,129,129,129
BEGIN DESCRIPTION:
Johnson Creek 75.1
END DESCRIPTION:
XS GIS Cut Line= 4
      1857440.85     13968110.28      1857196.07     13967771.75
      1856969.51     13967638.94      1856639.41     13967204.87
#Sta/Elev= 30
  4394.9  1886.5  4496.4 1878.32  4567.5 1864.88  4705.6 1860.41  4739.2 1858.84
  4817.9 1845.99    4841 1846.28  4993.8 1846.42  5004.2 1842.93  5005.7 1841.93
  5069.4 1842.93  5073.9 1857.38    5158 1860.61    5311 1859.96  5381.7  1863.9
  5388.2 1866.89    5409 1870.68  5438.1 1881.04  5452.6 1892.41  5458.9 1893.82
    5488 1909.35  5502.5 1922.18  5508.8 1923.43  5517.1 1931.74  5523.4 1933.21
  5531.6 1939.56  5537.9 1940.75  5552.4 1952.89  5602.4 1976.75  5620.6 1981.45
#Mann= 7 ,-1 , 0
  4394.9     .07       0  4705.6      .1       0    4841    .033       0
  5004.2    .033       0  5069.4    .033       0    5158     .05       0
    5311      .1       0
Bank Sta=5004.2,5069.4
XS Rating Curve= 0 ,0
Exp/Cntr=0.3,0.1

Type RM Length L Ch R = 1 ,66694   ,703,703,703
BEGIN DESCRIPTION:
Johnson Creek 75.0
END DESCRIPTION:
XS GIS Cut Line= 3
      1857479.92     13967969.66        1857075.       13967575.
      1856775.02     13967175.03
#Sta/Elev= 30
  4439.2 1877.49  4509.6 1874.94  4559.1 1862.63  4709.8 1858.85  4744.6 1856.32
  4785.4 1848.81  4806.7 1840.21  4926.8 1840.04  4943.8  1838.1  4945.3  1837.1
    5009  1838.1  5041.1 1842.76  5047.3 1849.74  5068.2 1860.28  5163.3 1858.66
  5254.6 1859.73  5282.8 1862.98  5297.3 1868.28  5326.5 1885.92  5347.3 1894.34
  5361.9 1906.78  5368.2 1908.39  5376.5 1915.09  5382.8 1916.07  5411.9 1939.44
  5418.2 1940.44  5426.5 1946.19  5447.3 1954.54  5461.9 1966.38  5504.6 1981.28
#Mann= 6 ,-1 , 0
  4439.2     .07       0  4709.8      .1       0  4744.6    .033       0
  4943.8     .05       0    5009    .033       0  5163.3      .1       0
Bank Sta=4943.8,5009
XS Rating Curve= 0 ,0
Exp/Cntr=0.3,0.1

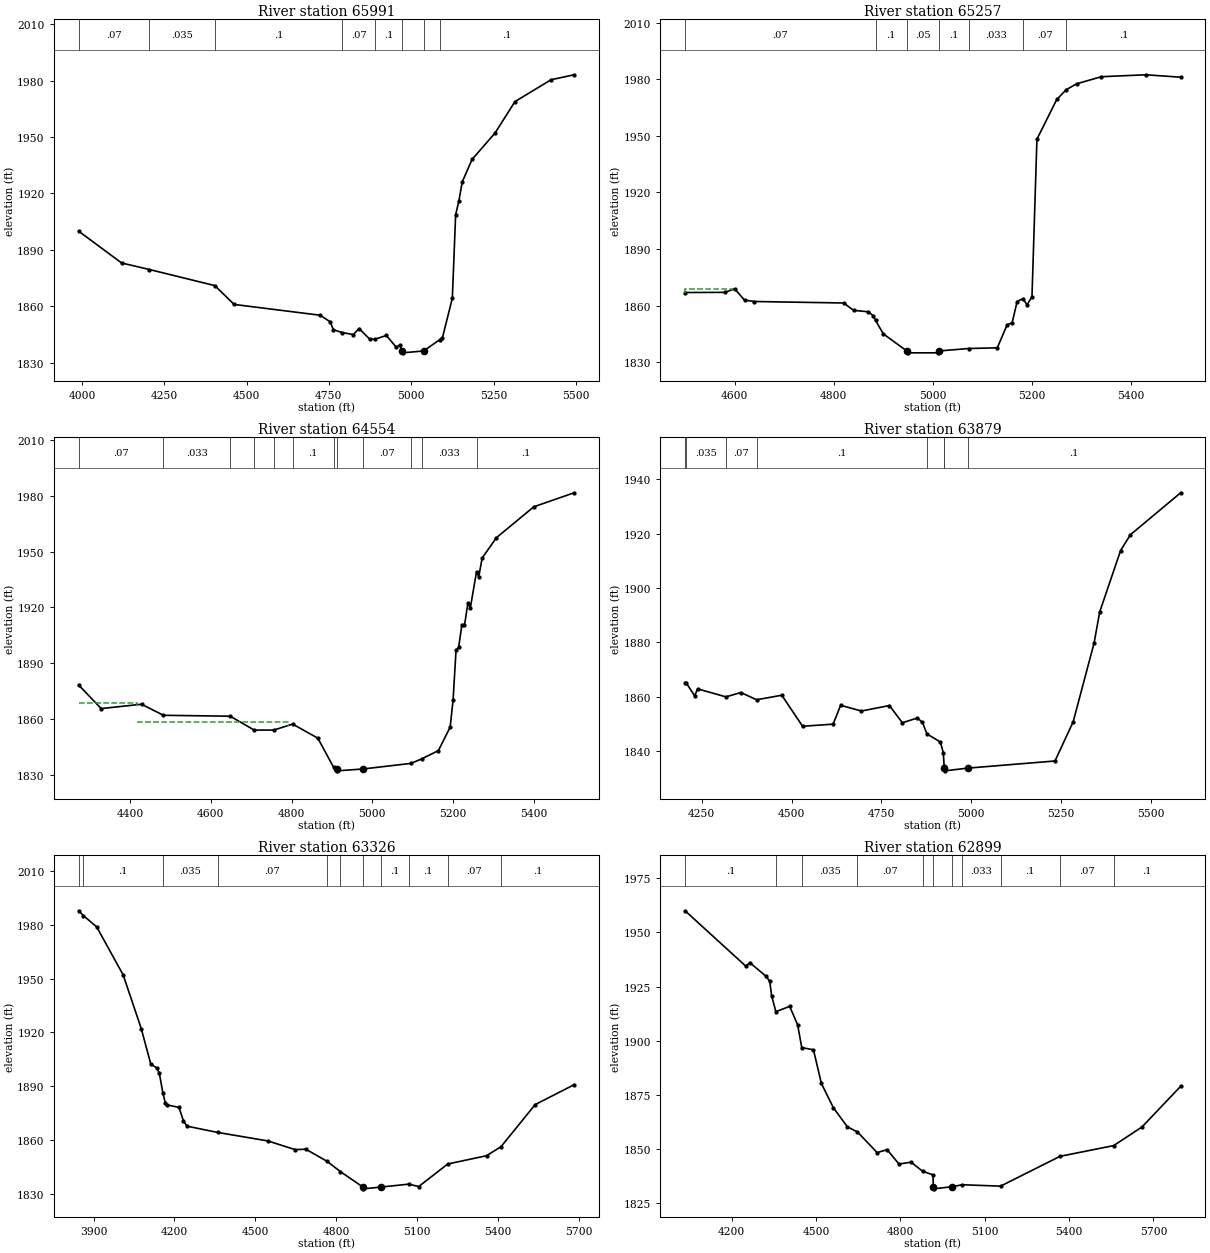
Type RM Length L Ch R = 1 ,65991   ,734,734,734
BEGIN DESCRIPTION:
Johnson Creek 74.0
END DESCRIPTION:
XS GIS Cut Line= 3
        1857625.     13968174.96        1857525.       13967175.
        1857525.     13966674.95
#Sta/Elev= 30
    3990 1899.91  4120.6 1882.98    4205 1879.51  4403.4 1870.97  4462.3 1860.95
  4723.6  1855.2  4753.8 1851.73  4763.8  1847.5  4790.4 1845.99  4824.1 1844.93
  4841.7 1848.15  4874.4 1842.43  4889.6 1842.43  4924.6 1844.45  4954.8 1838.16
  4964.8 1839.35  4972.4 1836.21  4973.9 1835.21  5037.6 1836.21  5087.1 1842.23
    5095 1843.29    5125 1864.26    5135 1908.59    5145 1916.08    5155 1926.08
    5185 1938.06    5255 1952.16    5315 1968.77    5425 1980.42    5495 1983.05
#Mann= 8 ,-1 , 0
    3990     .07       0    4205    .035       0  4403.4      .1       0
  4790.4     .07       0  4889.6      .1       0  4972.4     .05       0
  5037.6      .1       0  5087.1      .1       0
Bank Sta=4972.4,5037.6
XS Rating Curve= 0 ,0
Exp/Cntr=0.3,0.1

Type RM Length L Ch R = 1 ,65257   ,703,703,703
BEGIN DESCRIPTION:
Johnson Creek 73.0
END DESCRIPTION:
XS GIS Cut Line= 3
        1858225.     13967675.04        1858225.       13967175.
        1858225.     13966675.04
#Sta/Elev= 30
  4500.1 1866.93  4580.1 1867.02  4600.1  1868.9  4620.1 1862.89  4640.1 1862.17
  4820.1 1861.38  4840.1 1857.48  4870.1 1856.71  4880.1 1854.51  4884.4 1852.17
  4900.1    1845  4947.5 1835.95    4949 1834.95  5011.2 1834.95  5012.7 1835.95
  5072.5 1837.25  5130.1 1837.61  5150.1 1849.89  5160.1  1850.9  5170.1 1862.13
  5181.6 1863.73  5190.1 1860.43  5200.1 1864.67  5210.1 1948.22  5250.1 1969.29
  5269.2 1974.46  5290.1 1977.59  5340.1 1981.36  5430.1 1982.38  5500.1 1981.09
#Mann= 7 ,-1 , 0
  4500.1     .07       0  4884.4      .1       0  4947.5     .05       0
  5012.7      .1       0  5072.5    .033       0  5181.6     .07       0
  5269.2      .1       0
#XS Ineff= 2 , 0
          4596.6 1868.86 5181.62         1863.11
Permanent Ineff=
       F       F
#Block Obstruct= 2 , 0
          4600.2  1868.5
Bank Sta=4947.5,5012.7
XS Rating Curve= 0 ,0
Exp/Cntr=0.3,0.1

Type RM Length L Ch R = 1 ,64554   ,675,675,675
BEGIN DESCRIPTION:
Johnson Creek 72.0
END DESCRIPTION:
XS GIS Cut Line= 3
      1858624.99     13967925.03        1858825.       13967225.
      1858525.03     13966825.04
#Sta/Elev= 30
  4272.4 1878.22  4328.3 1865.53  4428.4 1867.86  4482.4 1861.91  4648.1 1861.41
  4707.4 1853.94  4755.7 1853.93  4802.7 1857.17  4865.2 1849.58    4904 1833.96
  4911.9 1832.98  4913.4 1831.98  4977.1 1832.98  5096.2    1836  5122.1 1838.39
    5164 1842.88  5193.2 1855.62  5200.4 1870.39  5207.7  1897.1    5214 1898.45
  5222.3 1910.79  5228.6 1910.33  5236.9 1922.16  5243.2 1919.89  5258.4 1939.22
    5264 1936.55  5272.3 1946.62  5307.7 1957.59  5400.4 1974.24  5500.4 1981.79
#Mann= 12 ,-1 , 0
  4272.4     .07       0  4482.4    .033       0  4648.1     .07       0
  4707.4      .1       0  4755.7    .033       0  4802.7      .1       0
    4904     .07       0  4911.9     .05       0  4977.1     .07       0
  5096.2      .1       0  5122.1    .033       0  5258.4      .1       0
#XS Ineff= 2 ,-1
  4272.4 4418.18  1868.5 4418.18 4790.21 1858.44
Permanent Ineff=
       F       F
#Block Obstruct= 2 , 0
         4422.38 1867.78
Bank Sta=4911.9,4977.1
XS Rating Curve= 0 ,0
Exp/Cntr=0.3,0.1

Type RM Length L Ch R = 1 ,63879   ,553,553,553
BEGIN DESCRIPTION:
Johnson Creek 71.0
END DESCRIPTION:
XS GIS Cut Line= 3
      1858936.07     13968004.28        1859425.       13967375.
        1859125.       13966875.
#Sta/Elev= 30
  4203.6 1865.16  4206.1 1865.16  4230.3 1860.26  4238.5 1862.84  4317.4 1859.89
  4358.8  1861.5  4402.7 1858.83  4472.9  1860.5  4530.8 1849.06  4615.9 1849.84
  4636.7 1856.79  4694.6 1854.68  4772.6  1856.7  4808.6 1850.36  4850.3  1852.1
  4864.7 1850.48  4876.9 1846.26  4914.5 1843.26  4922.7 1839.28  4924.9 1834.51
  4925.3 1833.64  4926.8 1832.64  4990.6 1833.64  5233.7 1836.27  5284.3  1850.7
  5342.6 1879.74  5358.1 1891.14  5416.4 1913.81  5443.7 1919.63  5583.6 1935.09
#Mann= 8 ,-1 , 0
  4203.6     .07       0  4206.1    .035       0  4317.4     .07       0
  4402.7      .1       0  4876.9     .07       0  4924.9      .1       0
  4925.3     .05       0  4990.6      .1       0
#Block Obstruct= 2 , 0
         4639.16 1854.97
Bank Sta=4925.3,4990.6
XS Rating Curve= 0 ,0
Exp/Cntr=0.3,0.1

Type RM Length L Ch R = 1 ,63326   ,427,427,427
BEGIN DESCRIPTION:
Johnson Creek 70.0
END DESCRIPTION:
XS GIS Cut Line= 3
        1860425.       13968325.      1859923.67     13967315.68
        1859525.       13966725.
#Sta/Elev= 30
  3844.2 1987.89  3861.5 1985.24  3911.2  1978.9  4009.5 1952.12  4076.7 1922.16
  4112.2 1902.32  4134.5 1900.25  4143.9  1897.2  4156.9 1886.22  4166.3 1880.56
  4171.9 1879.63  4216.7  1878.2  4233.5 1870.65  4246.2 1867.75  4359.8 1864.27
  4547.2  1859.5  4648.1 1854.64  4687.2 1854.92  4766.7 1848.13  4815.8 1842.41
  4899.7 1833.79  4901.2 1832.79  4967.7 1833.79  5069.4 1835.41  5106.8 1834.08
  5214.3 1846.64  5358.6 1851.28  5412.4 1856.33    5539 1879.78  5683.8 1890.89
#Mann= 11 ,-1 , 0
  3844.2     .07       0  3861.5      .1       0  4156.9    .035       0
  4359.8     .07       0  4766.7      .1       0  4815.8      .1       0
  4899.7     .05       0  4967.7      .1       0  5069.4      .1       0
  5214.3     .07       0  5412.4      .1       0
Bank Sta=4899.7,4967.7
XS Rating Curve= 0 ,0
Exp/Cntr=0.3,0.1

Type RM Length L Ch R = 1 ,62899   ,679,679,679
BEGIN DESCRIPTION:
Mapping XS c590356a
END DESCRIPTION:
XS GIS Cut Line= 3
      1860907.45     13968007.73      1860276.22     13967335.18
      1859665.35     13966759.88
#Sta/Elev= 30
    4035 1960.01  4250.9 1934.39  4265.1 1936.04  4321.7 1929.84  4335.9 1927.43
  4342.7 1920.63  4357.7 1913.36  4406.7 1915.82    4435 1907.33  4449.7 1896.77
  4491.3 1895.73  4519.5 1880.17    4562 1868.98  4611.8 1860.14  4647.8 1857.73
  4717.8 1848.21    4753 1849.57  4795.5 1842.91    4838 1843.81    4879 1839.62
  4916.1 1837.91  4917.3 1832.46  4918.8 1831.46  4985.3 1832.46  5019.8 1833.35
  5156.4 1832.71  5367.8 1846.49  5558.5 1851.45  5658.9 1860.04  5796.5 1878.84
#Mann= 11 ,-1 , 0
    4035      .1       0  4357.7     .07       0  4449.7    .035       0
  4647.8     .07       0    4879      .1       0  4917.3     .05       0
  4985.3      .1       0  5019.8    .033       0  5156.4      .1       0
  5367.8     .07       0  5558.5      .1       0
Bank Sta=4917.3,4985.3
XS Rating Curve= 0 ,0
Exp/Cntr=0.3,0.1

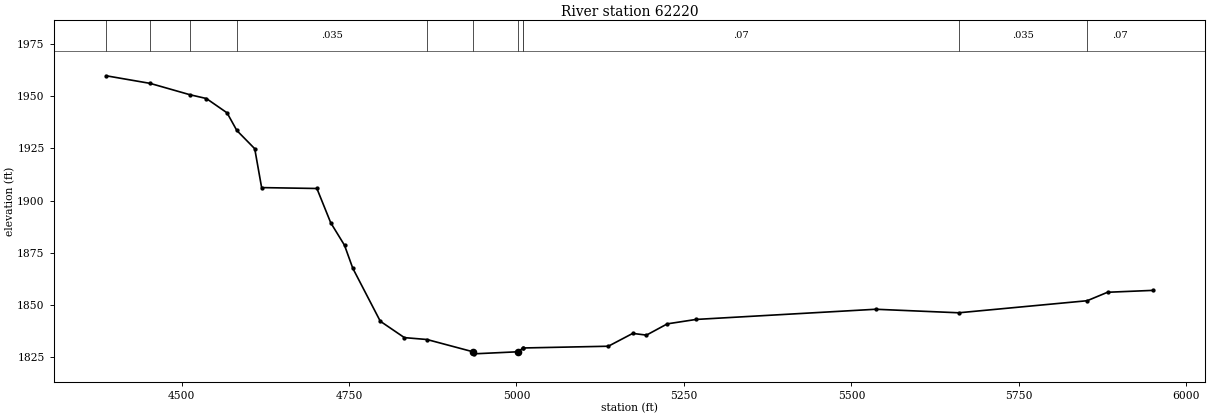
Type RM Length L Ch R = 1 ,62220   ,404,404,404
BEGIN DESCRIPTION:
Johnson Creek 69.1
END DESCRIPTION:
XS GIS Cut Line= 4
      1860899.13     13967719.96      1860770.23     13967208.26
       1860753.3     13967066.33      1859910.81     13966773.35
#Sta/Elev= 30
  4387.6 1959.79  4453.2 1956.15  4512.7 1950.71  4537.1 1948.91    4568 1942.05
  4582.6  1933.6  4609.3 1924.88  4619.6 1906.27  4702.1 1905.84  4722.7 1889.46
  4743.3 1878.67  4755.6 1867.71  4796.7 1842.31  4832.7 1834.46  4866.4 1833.56
  4934.9  1827.7  4936.4  1826.7  5002.9  1827.7  5009.3 1829.47  5010.2 1829.51
  5137.1 1830.34  5173.5 1836.48    5194 1835.66  5225.1 1841.05  5268.2 1843.17
  5536.2 1848.04  5660.2 1846.35  5851.8 1852.12  5882.2 1856.17  5950.2 1857.08
#Mann= 11 ,-1 , 0
  4387.6     .07       0  4453.2      .1       0  4512.7     .07       0
  4582.6    .035       0  4866.4     .07       0  4934.9     .05       0
  5002.9     .07       0  5009.3    .033       0  5010.2     .07       0
  5660.2    .035       0  5851.8     .07       0
Bank Sta=4934.9,5002.9
XS Rating Curve= 0 ,0
Exp/Cntr=0.3,0.1