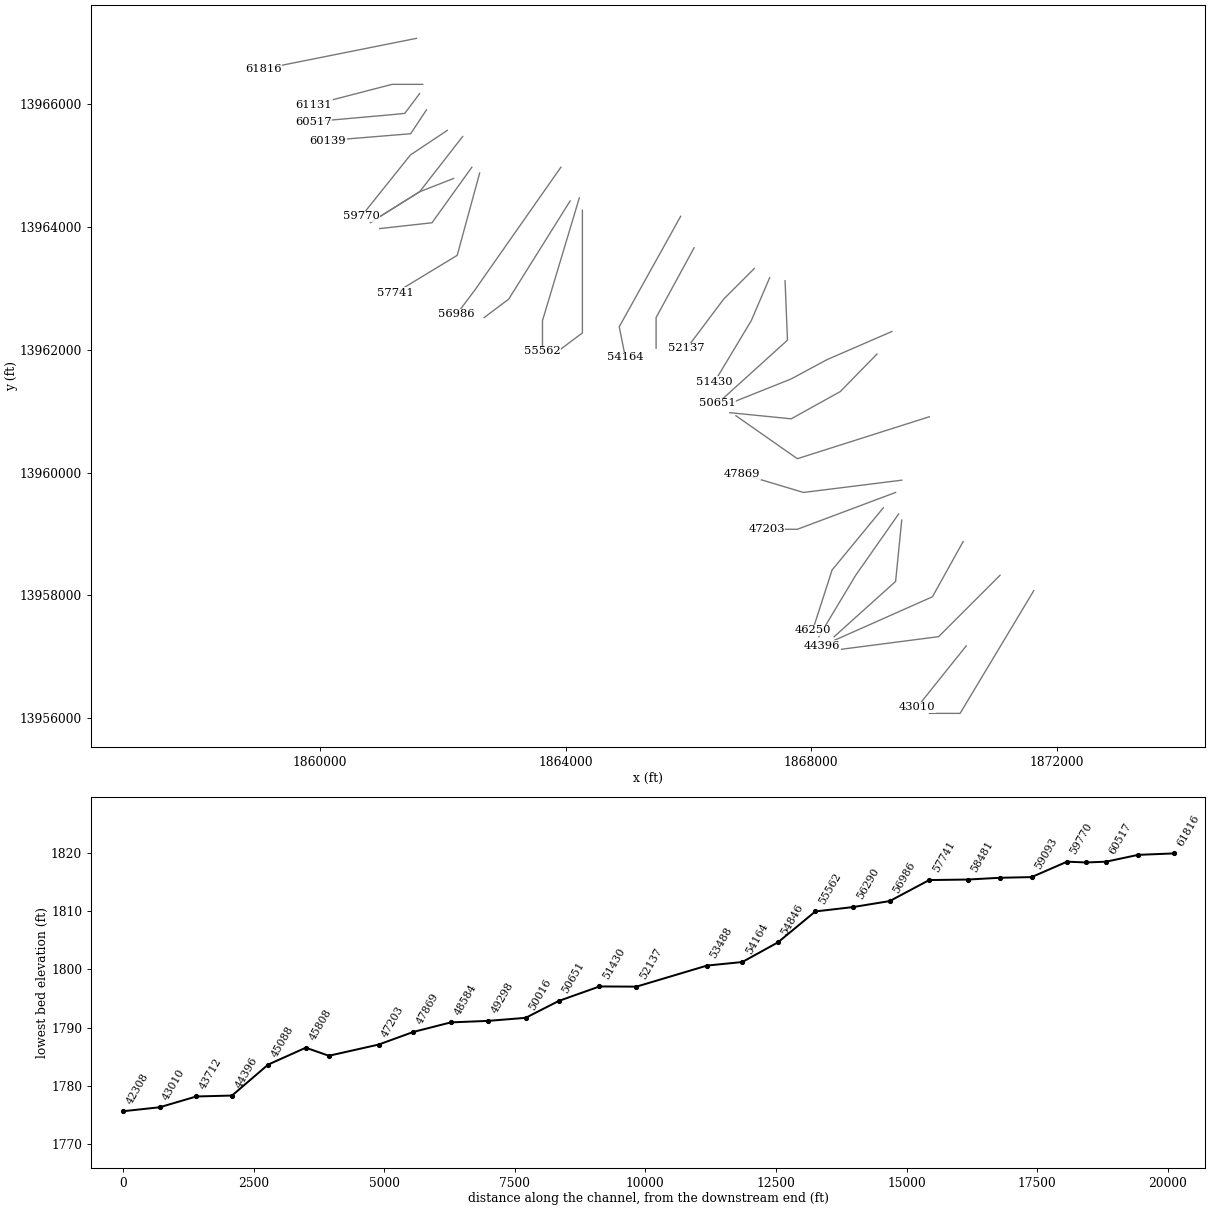
HEC-RAS study Johnson Creek.prj: Johnson Creek Base Level Engineering

--- Johnson Creek.g01 (geometry) --- (continued)

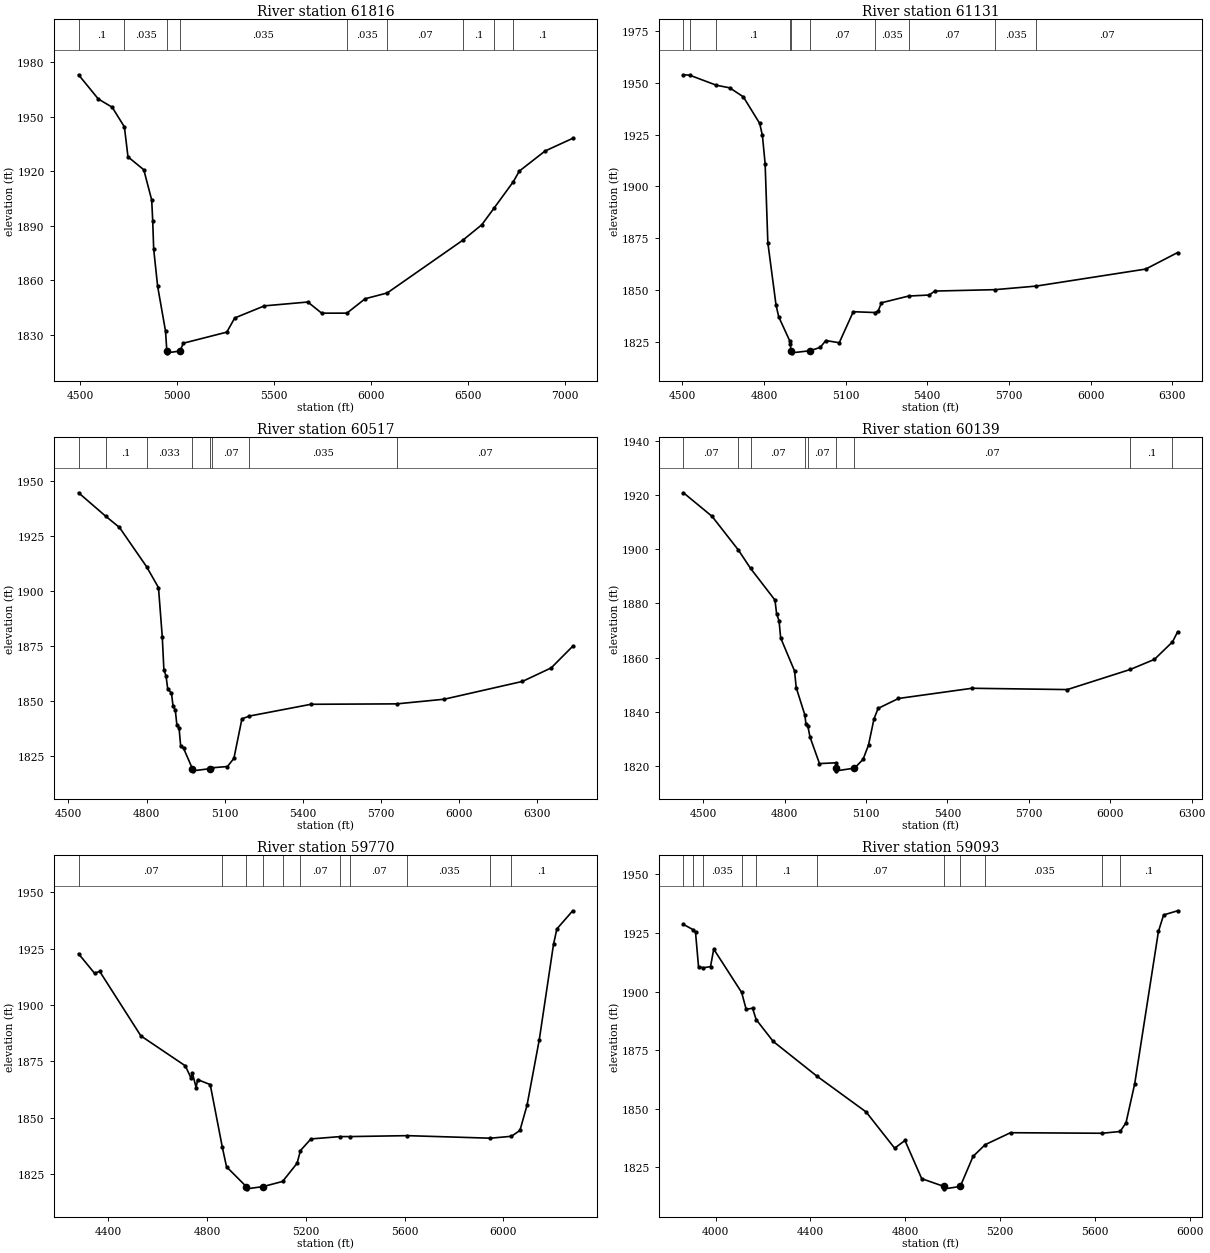
Type RM Length L Ch R = 1 ,61816   ,685,685,685
BEGIN DESCRIPTION:
Johnson Creek 69.0
END DESCRIPTION:
XS GIS Cut Line= 3
      1861575.03     13967075.01        1861075.       13966975.
      1859075.04     13966575.01
#Sta/Elev= 30
  4490.4 1973.21  4592.4 1959.85  4663.8 1955.33  4726.9 1944.47  4745.4 1927.96
    4827 1920.83  4867.8 1904.14  4872.9 1892.84    4878 1877.11  4898.4 1856.56
  4939.1 1831.86  4945.9 1820.89  4947.4 1819.89  5013.9 1820.89  5030.9  1825.2
  5255.3 1831.31  5296.1 1839.11    5449 1845.79  5673.4 1847.91  5744.8 1841.76
  5874.9 1841.78  5969.1 1849.71    6083 1852.91  6473.3 1882.02  6570.8  1890.5
  6633.4 1899.57  6733.3 1914.21  6764.6 1920.11  6897.2 1931.16  7039.9 1938.17
#Mann= 9 ,-1 , 0
  4490.4      .1       0  4726.9    .035       0  4945.9    .035       0
  5013.9    .035       0  5874.9    .035       0    6083     .07       0
  6473.3      .1       0  6633.4     .07       0  6733.3      .1       0
Bank Sta=4945.9,5013.9
XS Rating Curve= 0 ,0
Exp/Cntr=0.3,0.1

Type RM Length L Ch R = 1 ,61131   ,614,614,614
BEGIN DESCRIPTION:
Johnson Creek 68.0
END DESCRIPTION:
XS GIS Cut Line= 3
      1861674.96       13966325.        1861175.       13966325.
      1859901.54     13965994.54
#Sta/Elev= 30
  4504.3 1953.94  4526.9 1953.75  4625.5 1948.88  4674.3 1947.63  4724.3 1943.28
  4784.3 1930.45  4794.3 1924.65  4804.3 1910.96  4814.3  1872.8  4844.3 1842.79
  4854.3    1837  4894.3 1825.55  4896.5 1823.69  4900.1 1820.64  4901.6 1819.64
  4968.4 1820.64  5006.8 1822.26  5027.1 1825.58  5076.6 1824.52  5128.2  1839.5
  5207.7 1839.11  5219.6 1839.79  5231.6 1843.82    5332 1847.08  5407.2 1847.56
  5427.8 1849.48  5648.6 1850.15  5800.3 1851.88  6202.7  1860.1  6319.9 1868.07
#Mann= 10 ,-1 , 0
  4504.3    .035       0  4526.9     .07       0  4625.5      .1       0
  4896.5     .07       0  4900.1     .05       0  4968.4     .07       0
  5207.7    .035       0    5332     .07       0  5648.6    .035       0
  5800.3     .07       0
Bank Sta=4900.1,4968.4
XS Rating Curve= 0 ,0
Exp/Cntr=0.3,0.1

Type RM Length L Ch R = 1 ,60517   ,378,378,378
BEGIN DESCRIPTION:
Johnson Creek 67.0
END DESCRIPTION:
XS GIS Cut Line= 4
      1861624.98     13966174.97       1861382.7     13965851.94
      1861190.12     13965832.81      1859892.59     13965717.04
#Sta/Elev= 30
  4538.7 1944.78  4642.6 1934.18    4696 1929.03  4800.2 1911.21    4846 1901.71
  4860.5 1879.46  4866.8 1864.41  4875.1 1861.54  4881.4 1855.81    4896 1853.74
  4902.2 1847.71  4910.5 1846.26  4916.8 1839.26  4925.1 1837.98  4931.4 1829.64
  4942.5 1828.69  4976.4 1819.47  4977.9 1818.47  5044.7 1819.47  5051.1 1819.85
    5111 1820.43    5136 1824.12  5166.9 1842.09  5195.4 1843.35  5432.3  1848.7
    5762 1848.89  5944.3    1851  6245.5 1859.09    6356 1865.23  6438.7 1875.05
#Mann= 8 ,-1 , 0
  4538.7     .07       0  4642.6      .1       0  4800.2    .033       0
  4976.4    .033       0  5044.7    .033       0  5051.1     .07       0
  5195.4    .035       0    5762     .07       0
Bank Sta=4976.4,5044.7
XS Rating Curve= 0 ,0
Exp/Cntr=0.3,0.1

Type RM Length L Ch R = 1 ,60139   ,369,369,369
BEGIN DESCRIPTION:
Mapping XS 1715aece
END DESCRIPTION:
XS GIS Cut Line= 3
      1861736.64     13965910.22      1861478.52     13965520.49
      1860129.93     13965409.57
#Sta/Elev= 30
  4427.7 1920.75  4533.1 1912.06  4630.1 1899.65  4674.8 1892.91  4764.8 1881.23
  4770.8 1876.21  4779.8  1873.6  4785.8 1867.29    4837 1855.11    4843 1849.02
    4875 1838.87  4879.1 1835.41  4886.2 1834.68  4893.8 1830.81  4928.8 1821.01
    4989  1821.3  4989.5 1819.34    4991 1818.34  5057.8 1819.34  5089.3 1822.55
  5109.4 1827.84  5129.5 1837.41  5144.8 1841.34  5219.8 1844.99  5490.7 1848.75
  5841.9 1848.27  6073.6 1855.67  6162.9 1859.39  6229.4 1865.83  6248.3 1869.53
#Mann= 9 ,-1 , 0
  4427.7     .07       0  4630.1    .035       0  4674.8     .07       0
    4875    .035       0  4886.2     .07       0  4989.5     .05       0
  5057.8     .07       0  6073.6      .1       0  6229.4     .07       0
Bank Sta=4989.5,5057.8
XS Rating Curve= 0 ,0
Exp/Cntr=0.3,0.1

Type RM Length L Ch R = 1 ,59770   ,677,677,677
BEGIN DESCRIPTION:
Johnson Creek 66.0
END DESCRIPTION:
XS GIS Cut Line= 3
      1862075.02     13965575.02        1861475.       13965175.
      1860674.98     13964174.97
#Sta/Elev= 30
  4278.8 1922.71  4343.4  1914.1  4364.5 1914.89  4531.2 1886.31  4711.5 1873.01
    4734 1867.67    4740 1869.73  4755.1 1863.41  4761.1 1866.91  4812.2 1864.71
  4861.4 1836.81  4878.3 1828.24  4958.3 1819.47  4959.8 1818.47  5026.6 1819.47
  5105.5 1821.76    5164 1829.81  5177.9 1835.47    5220  1840.6  5338.4 1841.64
  5379.3 1841.65  5610.6 1842.06  5947.5 1840.93  6032.5 1841.78  6066.9 1844.38
  6095.7 1855.59  6145.3 1884.65  6202.9 1926.91  6216.5 1933.74  6280.6 1941.79
#Mann= 11 ,-1 , 0
  4278.8     .07       0  4861.4      .1       0  4958.3     .05       0
  5026.6      .1       0  5105.5      .1       0  5177.9     .07       0
  5338.4    .035       0  5379.3     .07       0  5610.6    .035       0
  5947.5     .07       0  6032.5      .1       0
Bank Sta=4958.3,5026.6
XS Rating Curve= 0 ,0
Exp/Cntr=0.3,0.1

Type RM Length L Ch R = 1 ,59093   ,612,612,612
BEGIN DESCRIPTION:
Johnson Creek 65.0
END DESCRIPTION:
XS GIS Cut Line= 3
      1862325.02     13965475.02        1861625.       13964575.
        1860825.       13964075.
#Sta/Elev= 30
  3864.8 1928.62  3905.1 1926.39  3915.5 1925.36  3928.2 1910.63  3948.1 1910.12
  3978.8 1910.63  3992.4 1918.09  4110.1  1899.6  4129.1 1892.42  4156.2 1892.86
  4171.2 1888.05  4243.1 1878.72  4425.8 1864.03  4634.9 1848.63  4755.2 1833.16
  4798.7 1836.45  4869.3 1820.17  4963.6 1816.83  4965.1 1815.83  5031.9 1816.83
  5085.8 1829.66  5136.8 1834.66  5243.8 1839.77  5629.5 1839.54  5706.1 1840.29
  5730.8 1844.01  5767.4 1860.59  5867.6 1925.66  5889.4 1932.66  5948.4 1934.44
#Mann= 11 ,-1 , 0
  3864.8     .07       0  3905.1    .063       0  3948.1    .035       0
  4110.1     .07       0  4171.2      .1       0  4425.8     .07       0
  4963.6     .05       0  5031.9     .07       0  5136.8    .035       0
  5629.5     .07       0  5706.1      .1       0
Bank Sta=4963.6,5031.9
XS Rating Curve= 0 ,0
Exp/Cntr=0.3,0.1

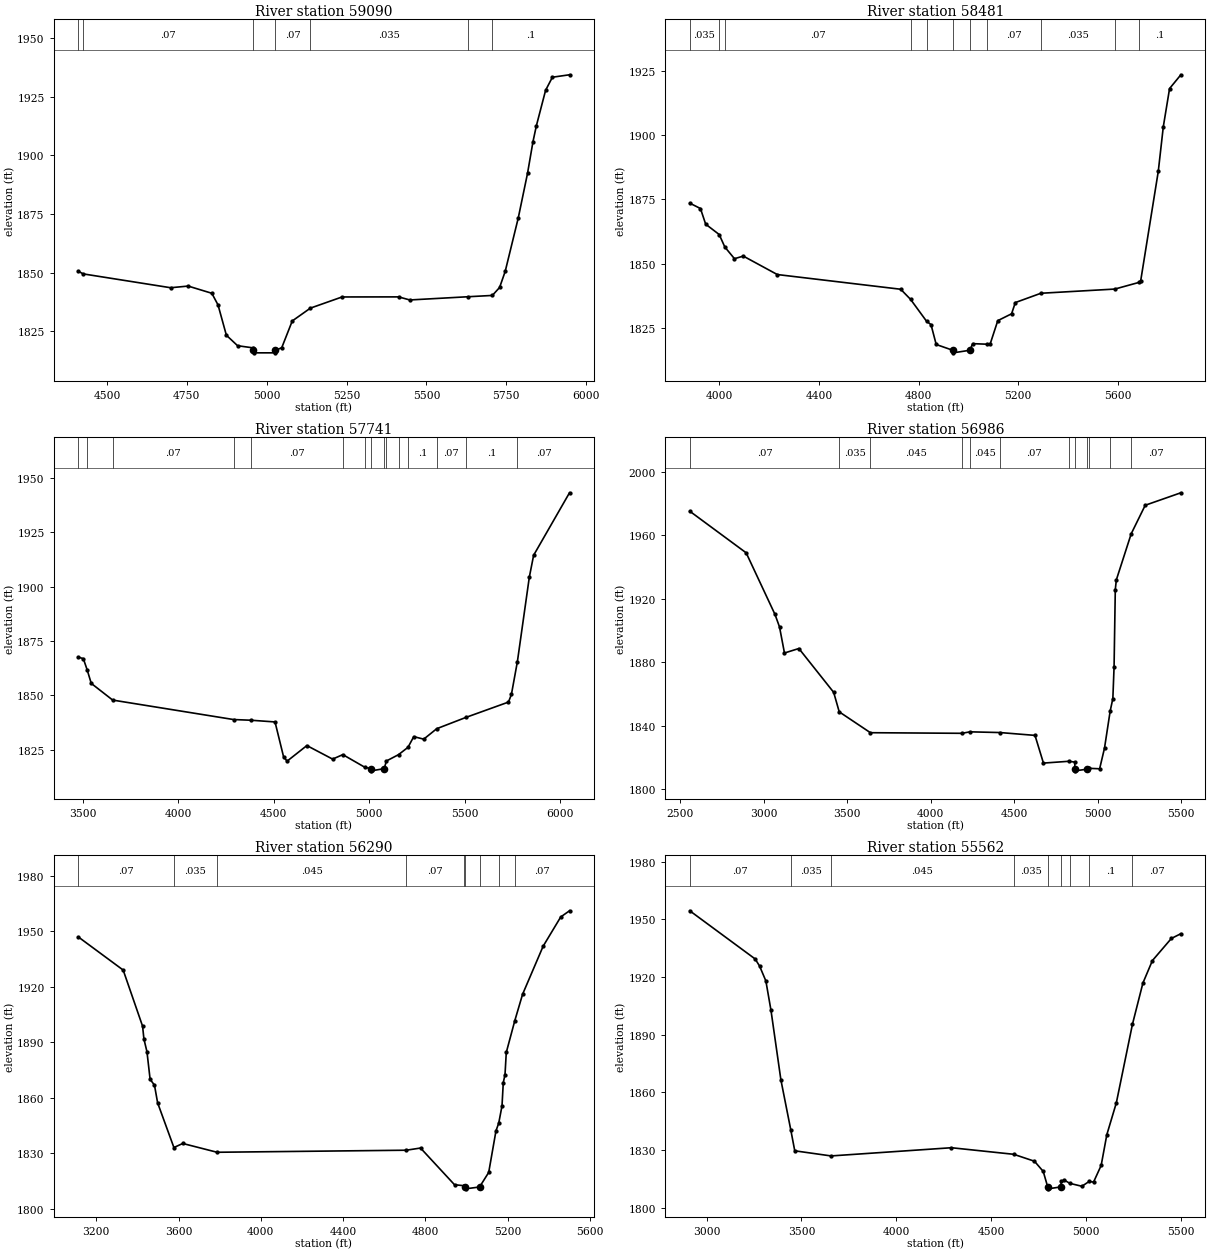
Type RM Length L Ch R = 1 ,59090   ,609,609,609
BEGIN DESCRIPTION:
Johnson Creek 65.0
END DESCRIPTION:
XS GIS Cut Line= 3
       1862177.4     13964791.47        1861625.       13964575.
        1860825.       13964075.
#Sta/Elev= 30
  4410.9 1850.55  4425.8 1849.42  4699.5 1843.51  4754.3 1844.22  4828.4 1841.14
  4847.8 1836.16  4873.9 1823.23    4909 1818.75  4957.3 1817.84  4958.6 1816.71
  4960.1 1815.71  5025.4 1815.71  5026.9 1816.71  5047.2 1817.92  5080.1 1829.33
  5136.8  1834.8  5235.9 1839.57  5412.8  1839.6  5447.9 1838.29  5629.5 1839.66
  5706.1 1840.22  5728.8 1843.61  5746.3 1850.45  5787.2 1873.28  5816.2 1892.33
  5833.4 1905.95  5843.8 1912.61  5872.8 1927.82  5894.1  1933.4  5947.6 1934.44
#Mann= 7 ,-1 , 0
  4410.9      .1       0  4425.8     .07       0  4958.6     .05       0
  5026.9     .07       0  5136.8    .035       0  5629.5     .07       0
  5706.1      .1       0
Bank Sta=4958.6,5026.9
XS Rating Curve= 0 ,0
Exp/Cntr=0.3,0.1

Type RM Length L Ch R = 1 ,58481   ,740,740,740
BEGIN DESCRIPTION:
Johnson Creek 64.0
END DESCRIPTION:
XS GIS Cut Line= 3
      1862474.97     13964974.96      1861826.03     13964069.59
      1860974.99       13963975.
#Sta/Elev= 30
  3882.2 1873.55  3925.1 1871.46    3946 1865.39  4000.2 1861.37  4022.9 1856.51
  4061.5 1851.98  4097.1 1852.98  4233.4 1845.82  4728.4 1840.11  4768.2 1836.16
  4832.7 1827.61    4850 1826.39  4870.9 1818.65  4937.4 1816.41  4938.9 1815.41
  5005.7 1816.41  5017.3 1818.98  5075.5 1818.76  5087.8 1818.98  5117.9 1827.91
  5173.3 1830.58  5188.3 1834.94  5290.9 1838.55  5587.5 1840.18  5686.4 1842.82
  5691.4 1843.48  5761.8 1885.89    5782 1903.25  5807.1 1918.06  5852.4 1923.41
#Mann= 11 ,-1 , 0
  3882.2    .035       0  4000.2      .1       0  4022.9     .07       0
  4768.2      .1       0  4832.7    .033       0  4937.4    .033       0
  5005.7    .033       0  5075.5     .07       0  5290.9    .035       0
  5587.5     .07       0  5686.4      .1       0
Bank Sta=4937.4,5005.7
XS Rating Curve= 0 ,0
Exp/Cntr=0.3,0.1

Type RM Length L Ch R = 1 ,57741   ,755,755,755
BEGIN DESCRIPTION:
Johnson Creek 63.0
END DESCRIPTION:
XS GIS Cut Line= 3
      1862602.25     13964879.89      1862236.24     13963538.44
      1861225.04     13962925.02
#Sta/Elev= 30
  3476.9 1867.63  3502.7 1866.95  3522.7  1861.8  3544.2 1855.56  3656.5 1847.88
  4290.1 1838.92  4380.7 1838.61  4507.1 1837.82    4552 1821.74  4570.4 1819.78
    4674 1826.95  4808.8 1820.72  4862.4 1822.78  4977.7 1816.96  5009.6 1816.32
  5011.1 1815.32    5079 1816.32  5090.8 1819.86  5154.1 1822.76  5203.9 1826.15
    5234 1831.06  5286.3  1829.9  5354.4 1834.71  5507.1  1839.9  5730.3 1846.96
  5745.7 1850.48  5776.9  1865.5  5839.6 1904.47  5862.1 1914.52  6050.1 1943.27
#Mann= 15 ,-1 , 0
  3476.9    .063       0  3522.7    .035       0  3656.5     .07       0
  4290.1    .035       0  4380.7     .07       0  4862.4    .035       0
  4977.7     .07       0  5009.6     .05       0    5079     .07       0
  5090.8    .035       0  5154.1     .07       0  5203.9      .1       0
  5354.4     .07       0  5507.1      .1       0  5776.9     .07       0
Bank Sta=5009.6,5079
XS Rating Curve= 0 ,0
Exp/Cntr=0.3,0.1

Type RM Length L Ch R = 1 ,56986   ,696,696,696
BEGIN DESCRIPTION:
Johnson Creek 62.0
END DESCRIPTION:
XS GIS Cut Line= 3
      1863924.99     13964974.98        1862525.       13962975.
        1862225.     13962574.99
#Sta/Elev= 30
  2557.5 1975.26  2895.3 1949.05    3068 1910.23    3095 1902.38  3124.7 1885.95
    3211 1888.77  3419.4 1861.17  3452.7 1848.88  3639.6 1835.74  4187.5 1835.36
  4235.8 1836.29  4415.1 1835.84  4625.2 1834.05  4675.8  1816.6  4827.9 1817.74
  4863.2 1817.22  4864.3 1812.72  4865.8 1811.72  4933.7 1812.72  4950.7 1813.29
  5012.3 1813.02  5041.5 1826.04  5075.5 1849.42  5091.5 1857.26  5098.8 1877.26
  5106.1 1925.87  5112.3 1931.98  5201.4 1961.05  5285.3 1979.01  5498.8 1986.87
#Mann= 12 ,-1 , 0
  2557.5     .07       0  3452.7    .035       0  3639.6    .045       0
  4187.5     .07       0  4235.8    .045       0  4415.1     .07       0
  4827.9      .1       0  4864.3     .05       0  4933.7      .1       0
  4950.7     .07       0  5075.5      .1       0  5201.4     .07       0
#Block Obstruct= 2 , 0
         4247.25 1836.73
Bank Sta=4864.3,4933.7
XS Rating Curve= 0 ,0
Exp/Cntr=0.3,0.1

Type RM Length L Ch R = 1 ,56290   ,728,728,728
BEGIN DESCRIPTION:
Johnson Creek 61.0
END DESCRIPTION:
XS GIS Cut Line= 3
      1864075.01     13964425.01        1863075.       13962825.
      1862675.01     13962525.01
#Sta/Elev= 30
  3113.2 1946.76  3330.8  1928.9  3425.1 1898.58  3431.6 1891.65  3446.4 1884.77
  3461.7 1869.85  3482.9 1866.73  3498.2 1857.16  3577.3 1833.02  3620.3 1835.21
  3787.2 1830.46  4706.9 1831.57    4776 1832.75  4941.1 1812.92  4989.5 1812.37
  4993.4  1811.7  4994.9  1810.7  5062.8  1811.7  5107.3 1819.57  5142.7 1842.07
    5156  1846.2  5171.9 1855.47  5178.1 1868.05  5186.5  1872.4  5192.7 1884.38
  5234.3 1901.64  5271.9 1915.81  5371.9  1941.8  5457.3 1957.59    5500 1960.94
#Mann= 9 ,-1 , 0
  3113.2     .07       0  3577.3    .035       0  3787.2    .045       0
  4706.9     .07       0  4989.5    .033       0  4993.4    .033       0
  5062.8    .033       0    5156      .1       0  5234.3     .07       0
#Block Obstruct= 2 , 0
         4753.25 1833.05
Bank Sta=4993.4,5062.8
XS Rating Curve= 0 ,0
Exp/Cntr=0.3,0.1

Type RM Length L Ch R = 1 ,55562   ,716,716,716
BEGIN DESCRIPTION:
Johnson Creek 60.0
END DESCRIPTION:
XS GIS Cut Line= 3
      1864224.99     13964474.98        1863625.       13962475.
        1863625.     13961975.04
#Sta/Elev= 30
  2911.6 1954.42  3256.1 1929.39  3279.6 1925.69  3312.7 1917.96  3339.6  1902.7
  3391.8 1866.58  3443.9  1840.6  3464.9  1829.7  3656.1 1827.04  4290.6  1831.3
  4618.7 1827.89  4728.2 1824.28  4774.3 1818.99  4797.9 1810.94  4799.4 1809.94
  4867.3 1810.94  4869.1 1813.88  4884.8 1814.53    4914 1812.81  4977.9 1811.27
  5016.2 1813.78  5039.6 1813.46  5079.6 1822.11  5109.6 1838.13  5159.6 1854.64
  5244.4 1895.42  5299.6 1916.87  5349.6 1928.54  5449.6 1940.04  5499.6 1942.51
#Mann= 9 ,-1 , 0
  2911.6     .07       0  3443.9    .035       0  3656.1    .045       0
  4618.7    .035       0  4797.9    .033       0  4867.3    .035       0
    4914    .033       0  5016.2      .1       0  5244.4     .07       0
#Block Obstruct= 2 , 0
          4295.2 1831.94
Bank Sta=4797.9,4867.3
XS Rating Curve= 0 ,0
Exp/Cntr=0.3,0.1

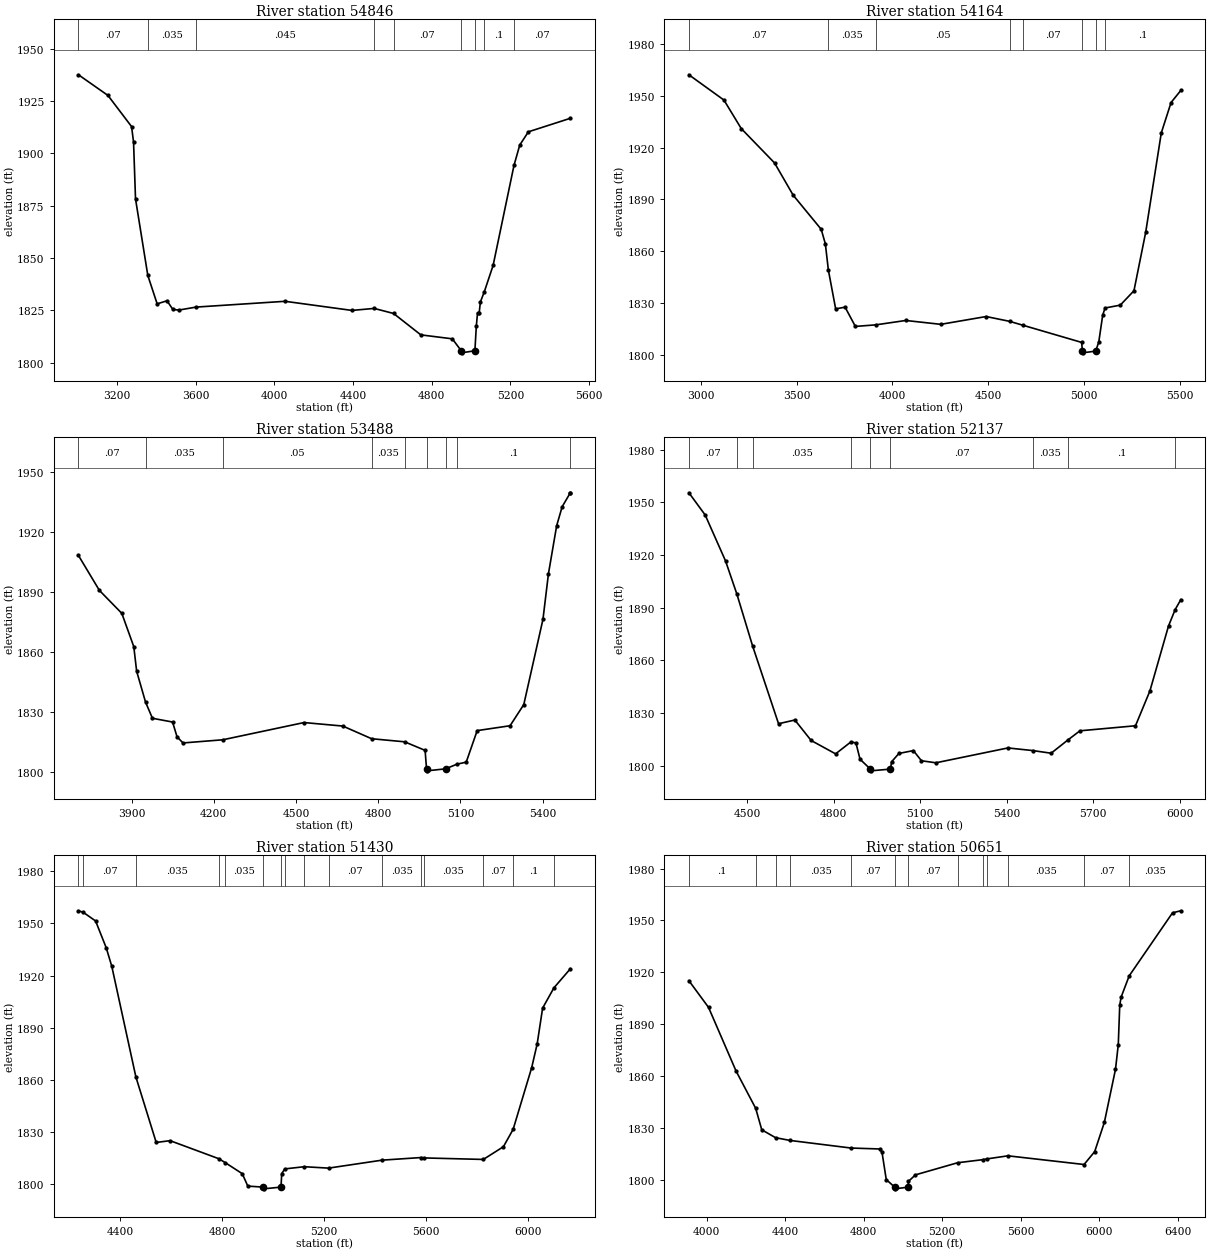
Type RM Length L Ch R = 1 ,54846   ,682,682,682
BEGIN DESCRIPTION:
Johnson Creek 59.0
END DESCRIPTION:
XS GIS Cut Line= 3
        1864275.     13964275.01        1864275.       13962275.
      1863875.01     13961975.01
#Sta/Elev= 30
  3004.5 1937.58  3154.5  1927.7  3274.5 1912.81  3284.5 1905.41  3294.5 1878.26
    3357 1841.64  3404.5 1828.06  3454.5 1829.53  3484.5 1825.37  3514.5 1825.09
  3602.9 1826.52  4054.5 1829.28  4394.5 1824.92  4507.5 1825.88  4605.9 1823.46
  4744.5 1813.23  4904.5 1811.34  4949.8 1805.64  4951.3 1804.64  5019.3 1805.64
  5026.4  1817.3  5032.6 1823.66    5041 1823.77  5047.2 1828.96    5067 1833.82
  5111.8 1846.42    5218 1894.27  5247.2 1903.98    5291 1910.31  5504.5 1916.78
#Mann= 9 ,-1 , 0
  3004.5     .07       0    3357    .035       0  3602.9    .045       0
  4507.5    .035       0  4605.9     .07       0  4949.8     .05       0
  5019.3     .07       0    5067      .1       0    5218     .07       0
#Block Obstruct= 2 , 0
         4068.86 1829.34
Bank Sta=4949.8,5019.3
XS Rating Curve= 0 ,0
Exp/Cntr=0.3,0.1

Type RM Length L Ch R = 1 ,54164   ,676,676,676
BEGIN DESCRIPTION:
Johnson Creek 58.0
END DESCRIPTION:
XS GIS Cut Line= 3
      1865875.02     13964175.03        1864875.       13962375.
      1864975.01     13961874.96
#Sta/Elev= 30
  2936.9 1962.11    3120 1947.48  3210.3    1931  3384.2 1911.12  3481.5 1892.46
  3627.9 1872.73  3649.6 1864.31  3665.2 1849.24  3703.4 1826.69  3752.6  1827.7
  3806.3 1816.55  3911.9 1817.44  4069.5 1819.99  4252.5 1817.76  4489.3 1822.27
  4612.2 1819.48  4681.4 1817.23  4988.1  1807.3  4991.9 1802.27  4993.4 1801.27
  5061.4 1802.27  5077.6  1807.6    5098 1823.03  5110.2 1827.21  5189.8 1828.86
  5261.2 1837.17  5322.4  1870.9    5404 1928.47    5455 1946.05    5506 1953.07
#Mann= 8 ,-1 , 0
  2936.9     .07       0  3665.2    .035       0  3911.9     .05       0
  4612.2    .035       0  4681.4     .07       0  4991.9     .05       0
  5061.4     .07       0  5110.2      .1       0
#Block Obstruct= 2 , 0
         4456.09 1821.92
Bank Sta=4991.9,5061.4
XS Rating Curve= 0 ,0
Exp/Cntr=0.3,0.1

Type RM Length L Ch R = 1 ,53488   ,1351,1351,1351
BEGIN DESCRIPTION:
Johnson Creek 57.0
END DESCRIPTION:
XS GIS Cut Line= 3
      1866093.94     13963662.05        1865475.       13962525.
        1865475.     13962024.99
#Sta/Elev= 30
  3706.3 1908.24  3782.8 1890.78  3864.5 1879.33  3908.2 1862.68  3918.6 1850.41
  3951.1 1834.99  3976.2 1826.92  4049.7 1825.04  4065.9 1817.67  4087.7 1814.59
  4232.8 1816.17  4529.3 1824.78  4670.7 1823.03  4775.9  1816.7  4896.2 1815.16
    4971 1810.88  4976.1 1801.66  4977.6 1800.66  5045.6 1801.66    5087 1803.98
  5120.9    1805  5160.9 1820.76  5280.9 1823.19  5330.9 1833.75  5400.9 1876.34
  5420.9 1899.12  5450.9 1923.13  5470.9 1932.59  5500.7 1939.56  5500.9 1939.56
#Mann= 9 ,-1 , 0
  3706.3     .07       0  3951.1    .035       0  4232.8     .05       0
  4775.9    .035       0  4896.2     .07       0  4976.1     .05       0
  5045.6     .07       0    5087      .1       0  5500.7     .07       0
#Block Obstruct= 2 , 0
         4535.43 1823.75
Bank Sta=4976.1,5045.6
XS Rating Curve= 0 ,0
Exp/Cntr=0.3,0.1

Type RM Length L Ch R = 1 ,52137   ,707,707,707
BEGIN DESCRIPTION:
Johnson Creek 56.0
END DESCRIPTION:
XS GIS Cut Line= 3
      1867074.97     13963324.97        1866575.       13962825.
      1865974.98     13962024.97
#Sta/Elev= 30
  4297.4 1955.41  4353.9 1942.77  4424.6 1916.58  4463.9 1897.72  4518.6 1868.11
  4608.5 1823.88  4665.1    1826  4721.6 1814.34  4806.5 1806.72  4860.2 1813.59
  4877.2 1812.89  4891.3 1803.65  4927.3 1798.05  4928.8 1797.05  4996.8 1798.05
  5000.9 1802.23  5026.3 1806.96  5076.3 1808.58  5104.5 1802.79  5154.5 1801.63
  5404.5 1810.09    5491 1808.59  5554.5 1807.08  5612.6 1814.63  5654.5 1819.85
  5847.2 1822.72  5897.2 1842.54  5961.8 1879.56  5984.7 1888.83  6004.5 1894.56
#Mann= 9 ,-1 , 0
  4297.4     .07       0  4463.9      .1       0  4518.6    .035       0
  4860.2     .07       0  4927.3     .05       0  4996.8     .07       0
    5491    .035       0  5612.6      .1       0  5984.7     .07       0
#Block Obstruct= 2 , 0
         4860.68 1814.13
Bank Sta=4927.3,4996.8
XS Rating Curve= 0 ,0
Exp/Cntr=0.3,0.1

Type RM Length L Ch R = 1 ,51430   ,779,779,779
BEGIN DESCRIPTION:
Johnson Creek 55.0
END DESCRIPTION:
XS GIS Cut Line= 3
      1867325.01     13963175.03        1867025.       13962475.
        1866425.       13961475.
#Sta/Elev= 30
  4237.4 1957.32  4256.6 1956.39  4304.5 1951.46  4346.2 1936.01    4368 1925.34
  4462.5 1861.55  4542.1 1823.81  4596.5 1824.84    4788 1814.41  4813.3 1812.11
  4879.3 1805.82  4901.1 1798.65  4961.4 1798.08  4962.9 1797.08  5031.2 1798.08
    5034 1805.89  5046.1 1808.57  5122.4 1809.83  5217.5 1809.02  5427.2 1813.61
  5581.2 1815.13  5590.1  1814.9    5824 1814.02  5902.8 1821.36  5940.9 1831.37
  6013.6 1866.93    6035 1880.53  6056.4 1901.22  6100.7 1912.91  6165.2 1923.91
#Mann= 16 ,-1 , 0
  4237.4      .1       0  4256.6     .07       0  4462.5    .035       0
    4788     .07       0  4813.3    .035       0  4961.4    .035       0
  5031.2    .035       0  5046.1     .07       0  5122.4    .035       0
  5217.5     .07       0  5427.2    .035       0  5581.2     .07       0
  5590.1    .035       0    5824     .07       0  5940.9      .1       0
  6100.7     .07       0
Bank Sta=4961.4,5031.2
XS Rating Curve= 0 ,0
Exp/Cntr=0.3,0.1

Type RM Length L Ch R = 1 ,50651   ,635,635,635
BEGIN DESCRIPTION:
Johnson Creek 54.0
END DESCRIPTION:
XS GIS Cut Line= 3
        1867575.     13963125.04      1867614.58      13962156.8
      1866475.03     13961125.02
#Sta/Elev= 30
  3909.6 1915.14  4009.7 1899.67  4149.8 1862.85  4249.9 1841.22  4280.9 1828.79
  4351.1 1824.23  4424.6 1822.63  4735.9 1818.22  4881.7 1817.69  4893.5 1815.79
  4915.2 1799.95    4958  1795.6  4959.5  1794.6  5027.8  1795.6    5028  1798.9
  5063.9  1802.7  5278.7 1809.71    5406 1811.48  5430.6 1811.98  5535.2 1813.72
  5922.9 1808.69    5977 1816.14  6026.3 1833.07  6083.1 1863.83  6097.3 1878.17
  6104.7 1900.92  6111.5 1905.53  6152.9 1917.94  6373.7 1954.45  6415.9 1955.62
#Mann= 13 ,-1 , 0
  3909.6      .1       0  4249.9    .035       0  4351.1    .063       0
  4424.6    .035       0  4735.9     .07       0    4958     .05       0
  5027.8     .07       0  5278.7     .07       0    5406    .035       0
  5430.6     .07       0  5535.2    .035       0  5922.9     .07       0
  6152.9    .035       0
Bank Sta=4958,5027.8
XS Rating Curve= 0 ,0
Exp/Cntr=0.3,0.1

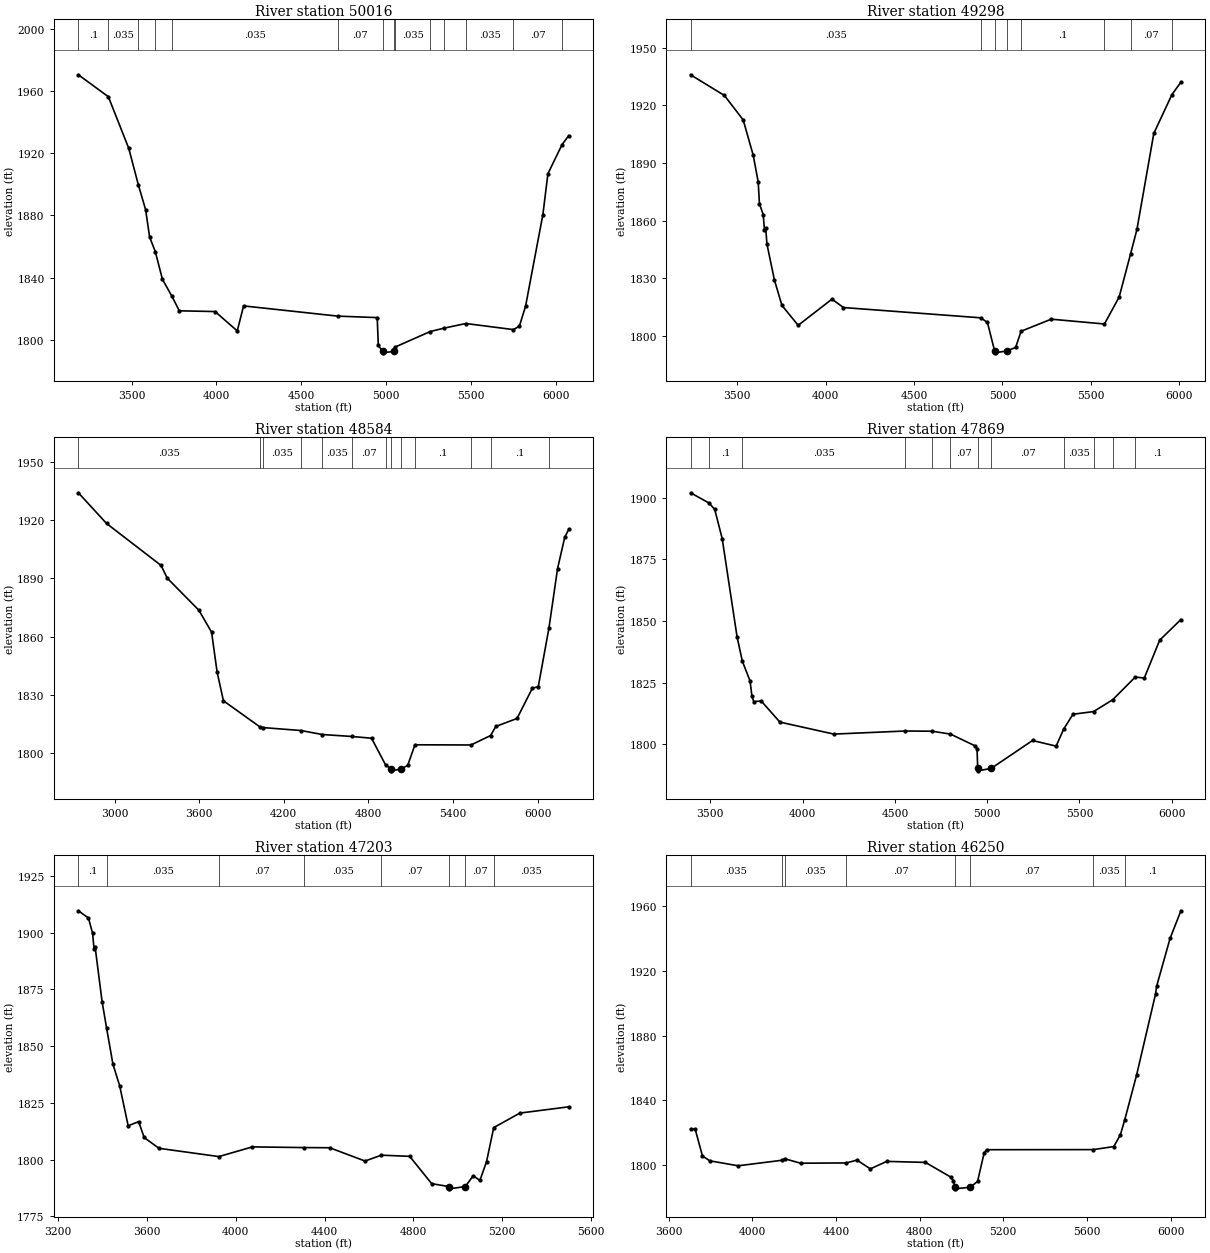
Type RM Length L Ch R = 1 ,50016   ,718,718,718
BEGIN DESCRIPTION:
Johnson Creek 53.0
END DESCRIPTION:
XS GIS Cut Line= 4
       1869314.2     13962297.68      1868258.62     13961839.34
        1867675.       13961525.      1866675.02     13961125.01
#Sta/Elev= 30
  3186.4 1970.31  3363.3  1956.2  3483.6    1923  3540.8 1899.27  3582.9 1883.66
  3606.3 1866.12  3639.7 1856.79  3682.2 1838.88  3738.6 1827.91  3781.4  1818.7
  3992.3 1818.22  4123.1 1805.79  4160.5 1821.85  4715.1 1815.29  4948.2 1814.33
  4954.7 1796.44    4980  1792.7  4981.5  1791.7  5049.8  1792.7  5054.8 1795.47
  5261.1  1805.4  5342.7 1807.58  5470.8 1810.54  5750.9 1806.63  5786.3 1808.82
  5822.7 1821.56    5925 1880.56  5954.6 1906.77  6037.7 1925.42  6077.1 1931.19
#Mann= 14 ,-1 , 0
  3186.4      .1       0  3363.3    .035       0  3540.8    .063       0
  3639.7     .07       0  3738.6    .035       0  4715.1     .07       0
    4980     .05       0  5049.8     .07       0  5054.8    .035       0
  5261.1     .07       0  5342.7      .1       0  5470.8    .035       0
  5750.9     .07       0  6037.7    .035       0
Bank Sta=4980,5049.8
XS Rating Curve= 0 ,0
Exp/Cntr=0.3,0.1

Type RM Length L Ch R = 1 ,49298   ,714,714,714
BEGIN DESCRIPTION:
Johnson Creek 52.0
END DESCRIPTION:
XS GIS Cut Line= 4
      1869071.13     13961929.62       1868473.9     13961318.51
        1867675.       13960875.      1866675.02       13960975.
#Sta/Elev= 30
    3236 1935.84  3427.4 1925.07  3533.6 1912.35  3590.2    1894  3618.5 1880.08
  3625.4 1868.77  3646.7 1863.15  3653.7 1855.34  3660.9 1856.12  3667.9 1847.78
  3710.3 1829.05  3752.7 1815.85  3844.6 1805.49  4035.6 1819.12  4100.7 1814.75
  4877.2  1809.4    4915 1806.98  4955.6 1792.18  4957.1 1791.18  5025.5 1792.18
  5074.6    1794  5105.2 1802.41  5275.6 1808.69  5576.7 1806.19    5660  1820.2
  5724.7  1842.7  5760.5 1855.36    5856 1905.34  5958.3  1925.5  6009.2 1931.99
#Mann= 8 ,-1 , 0
    3236    .035       0  4877.2     .07       0  4955.6     .05       0
  5025.5     .07       0  5105.2      .1       0  5576.7    .035       0
  5724.7     .07       0  5958.3    .035       0
Bank Sta=4955.6,5025.5
XS Rating Curve= 0 ,0
Exp/Cntr=0.3,0.1

Type RM Length L Ch R = 1 ,48584   ,715,715,715
BEGIN DESCRIPTION:
Johnson Creek 51.0
END DESCRIPTION:
XS GIS Cut Line= 3
      1869925.26     13960908.77        1867775.       13960225.
      1866775.01     13960924.99
#Sta/Elev= 30
  2743.6    1934  2943.2 1918.22  3329.9 1896.63  3373.5 1890.09  3598.3 1873.55
  3688.3 1862.26  3727.3 1841.81  3772.2 1826.97    4033 1813.43  4051.3 1813.19
  4322.7 1811.66    4473 1809.61  4682.5 1808.61  4822.6  1807.7  4921.7 1794.03
  4960.6 1791.92  4962.1 1790.92    5034 1791.92  5078.9 1793.73  5130.5 1804.32
  5527.9 1804.23  5666.4 1809.07    5704 1813.77  5854.4 1817.87    5963 1833.45
  6004.8 1834.22    6081 1864.56  6141.7 1895.03  6192.3 1911.02  6220.6 1915.11
#Mann= 13 ,-1 , 0
  2743.6    .035       0    4033     .07       0  4051.3    .035       0
  4322.7     .07       0    4473    .035       0  4682.5     .07       0
  4921.7      .1       0  4960.6     .05       0    5034      .1       0
  5130.5      .1       0  5527.9     .07       0  5666.4      .1       0
    6081     .07       0
Bank Sta=4960.6,5034
XS Rating Curve= 0 ,0
Exp/Cntr=0.3,0.1

Type RM Length L Ch R = 1 ,47869   ,666,666,666
BEGIN DESCRIPTION:
Johnson Creek 50.0
END DESCRIPTION:
XS GIS Cut Line= 3
        1869475.       13959875.        1867875.       13959675.
      1866874.98     13959975.01
#Sta/Elev= 30
    3393 1901.92  3493.8 1897.73    3524 1895.15  3564.3 1883.34  3644.9 1843.55
  3673.3 1833.74  3715.5 1825.63  3725.6 1819.41  3735.6 1817.35    3776 1817.56
  3876.7 1809.04    4169 1804.17  4556.8 1805.43  4702.1 1805.33    4801 1804.18
  4934.9 1799.39    4945 1798.32  4948.6 1790.29  4950.1 1789.29    5022 1790.29
  5245.6 1801.58  5373.5  1799.3  5414.4  1806.2  5464.8 1812.21  5576.3  1813.3
  5680.1 1818.09  5802.2 1827.28  5851.1 1826.88  5934.6 1842.22  6049.5 1850.58
#Mann= 12 ,-1 , 0
    3393     .07       0  3493.8      .1       0  3673.3    .035       0
  4556.8     .07       0  4702.1    .035       0    4801     .07       0
  4948.6     .05       0    5022     .07       0  5414.4    .035       0
  5576.3      .1       0  5680.1    .035       0  5802.2      .1       0
Bank Sta=4948.6,5022
XS Rating Curve= 0 ,0
Exp/Cntr=0.3,0.1

Type RM Length L Ch R = 1 ,47203   ,953,953,953
BEGIN DESCRIPTION:
Johnson Creek 49.0
END DESCRIPTION:
XS GIS Cut Line= 3
      1869375.04     13959675.02        1867775.       13959075.
      1867275.05       13959075.
#Sta/Elev= 30
    3291 1909.68  3336.4  1906.5  3355.1 1899.75  3361.4 1893.05  3366.7 1893.54
  3397.8 1869.67  3418.2 1857.94  3446.8 1842.01  3477.1 1832.54  3515.3  1814.9
  3562.5 1816.75  3587.4 1809.75  3654.2 1804.98  3923.8 1801.34  4075.1 1805.61
  4307.9 1805.31  4423.1 1805.23  4582.4 1799.37    4656 1801.96  4783.6 1801.44
  4882.4 1789.41  4960.4 1788.12  4961.9 1787.12  5033.9 1788.12  5069.8  1792.9
  5099.8  1790.8  5129.8 1799.14  5162.1 1814.11  5279.8 1820.51  5499.8 1823.27
#Mann= 8 ,-1 , 0
    3291      .1       0  3418.2    .035       0  3923.8     .07       0
  4307.9    .035       0    4656     .07       0  4960.4     .05       0
  5033.9     .07       0  5162.1    .035       0
Bank Sta=4960.4,5033.9
XS Rating Curve= 0 ,0
Exp/Cntr=0.3,0.1

Type RM Length L Ch R = 1 ,46250   ,442,442,442
BEGIN DESCRIPTION:
Johnson Creek 48.0
END DESCRIPTION:
XS GIS Cut Line= 3
      1869175.03     13959425.03       1868340.2     13958410.55
       1868024.5     13957429.62
#Sta/Elev= 30
  3705.2 1822.04  3726.8  1822.3  3761.9 1805.55  3797.1 1802.52  3932.7 1799.46
    4143 1802.88    4155 1803.82  4231.1 1801.05  4449.9 1801.23  4500.8 1802.97
  4564.7 1797.55  4642.9 1802.17    4828 1801.55  4948.5 1792.52  4962.2 1790.27
  4968.1  1786.2  4969.6  1785.2  5042.3  1786.2  5077.4 1789.79  5108.9 1807.53
  5121.1  1809.4  5630.2 1809.46  5728.7 1811.35  5760.2 1818.64  5781.4 1828.05
  5837.4 1855.45  5928.3 1905.69  5933.6  1910.6  5997.7 1940.07  6049.5 1957.17
#Mann= 8 ,-1 , 0
  3705.2    .035       0    4143     .07       0    4155    .035       0
  4449.9     .07       0  4968.1     .05       0  5042.3     .07       0
  5630.2    .035       0  5781.4      .1       0
Bank Sta=4968.1,5042.3
XS Rating Curve= 0 ,0
Exp/Cntr=0.3,0.1

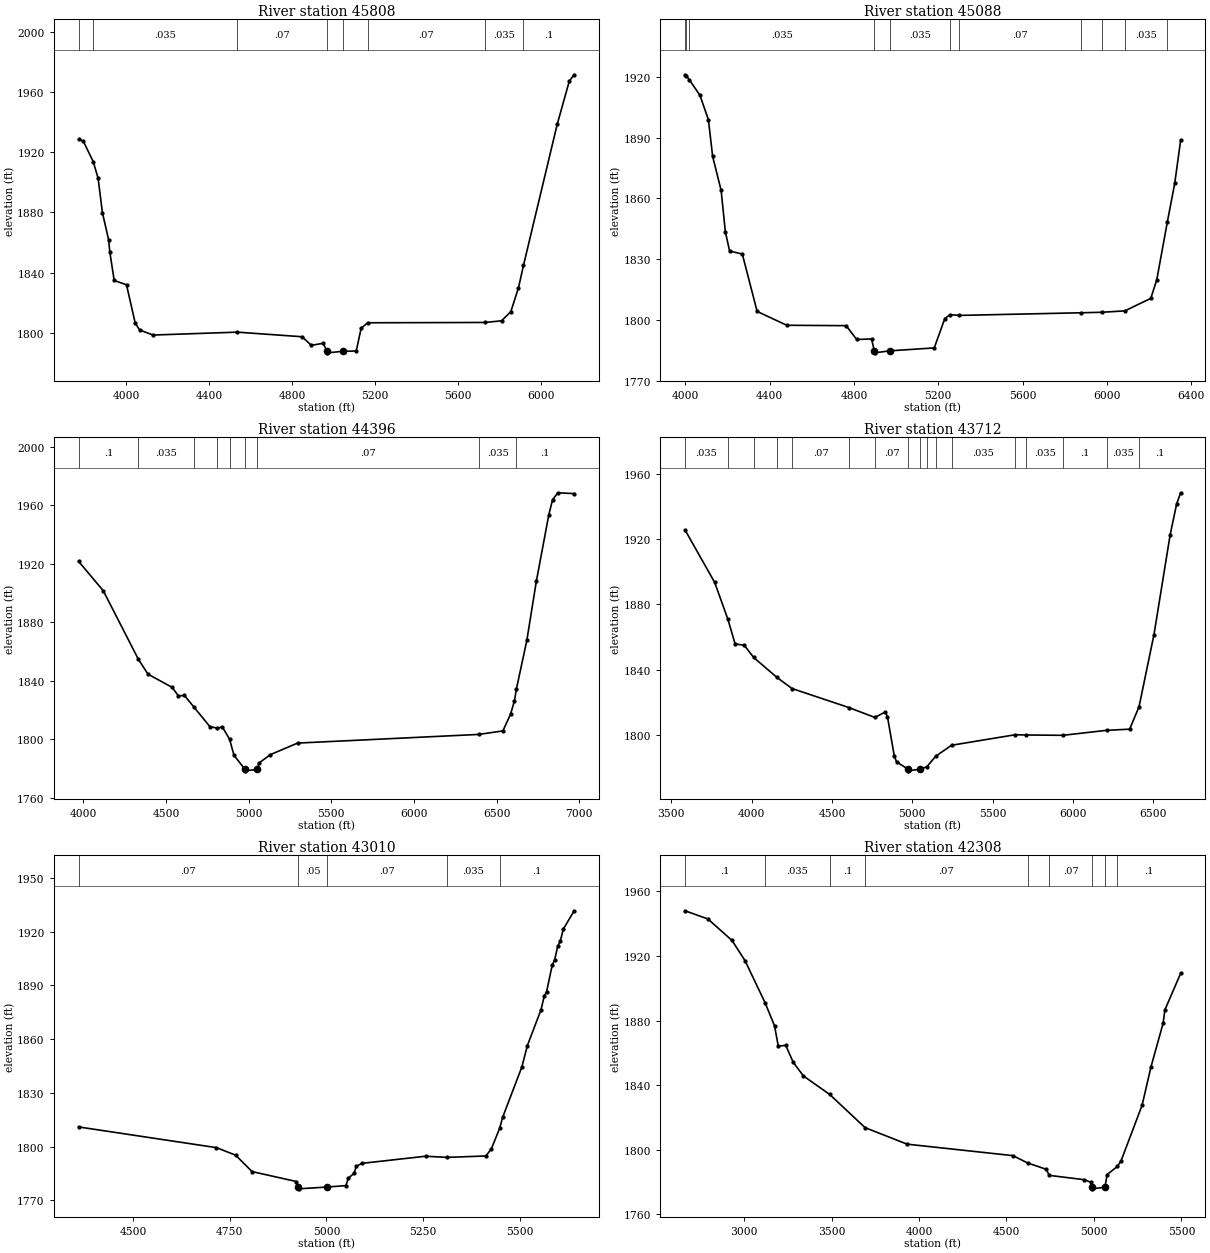
Type RM Length L Ch R = 1 ,45808   ,720,720,720
BEGIN DESCRIPTION:
Johnson Creek 47.0
END DESCRIPTION:
XS GIS Cut Line= 3
      1869424.98     13959324.97        1868725.       13958325.
      1868125.01     13957325.01
#Sta/Elev= 30
  3771.8 1928.55    3794 1927.53  3842.4 1913.65  3865.5 1902.83  3886.4 1879.82
  3916.1 1861.87  3922.2 1853.49  3943.1 1834.72  4002.4 1831.86  4044.2 1806.43
  4065.2  1801.8  4130.5 1798.42  4535.7 1800.35  4848.1 1797.29  4892.6 1791.57
  4949.3 1792.94  4968.9 1787.58  4970.4 1786.58  5043.1 1787.58    5109 1787.82
  5132.4  1802.9  5163.7 1806.58  5728.7 1806.79  5808.8  1807.9  5853.5 1813.99
  5890.4 1829.87  5914.4 1844.75    6077 1938.68  6135.3 1967.41  6158.6 1971.58
#Mann= 8 ,-1 , 0
  3771.8      .1       0  3842.4    .035       0  4535.7     .07       0
  4968.9     .05       0  5043.1     .07       0  5163.7     .07       0
  5728.7    .035       0  5914.4      .1       0
Bank Sta=4968.9,5043.1
XS Rating Curve= 0 ,0
Exp/Cntr=0.3,0.1

Type RM Length L Ch R = 1 ,45088   ,692,692,692
BEGIN DESCRIPTION:
Johnson Creek 46.0
END DESCRIPTION:
XS GIS Cut Line= 3
        1869475.     13959224.99        1869375.       13958225.
      1868375.03     13957325.02
#Sta/Elev= 30
  3999.4 1920.99  4004.6 1920.55  4019.9 1918.49  4069.7 1910.87  4109.9 1898.86
    4130  1880.7  4170.2 1863.94  4190.3  1843.5  4210.4 1833.95  4270.7 1832.49
  4341.1 1804.13  4481.8  1797.3  4763.2 1797.11  4813.4 1790.28  4883.8 1790.54
  4896.9 1784.69  4898.4 1783.69  4971.1 1784.69  5181.1 1786.12  5231.2 1800.62
    5257 1802.56  5298.9 1802.17  5879.4 1803.48  5975.6 1803.72  6085.1 1804.41
  6208.1 1810.58  6236.5 1819.77  6286.7 1848.35  6321.7 1867.41  6349.7 1888.62
#Mann= 11 ,-1 , 0
  3999.4     .07       0  4004.6      .1       0  4019.9    .035       0
  4896.9     .05       0  4971.1    .035       0    5257      .1       0
  5298.9     .07       0  5879.4    .035       0  5975.6     .07       0
  6085.1    .035       0  6286.7      .1       0
Bank Sta=4896.9,4971.1
XS Rating Curve= 0 ,0
Exp/Cntr=0.3,0.1

Type RM Length L Ch R = 1 ,44396   ,684,684,684
BEGIN DESCRIPTION:
Johnson Creek 45.0
END DESCRIPTION:
XS GIS Cut Line= 3
      1870474.98     13958874.96        1869975.       13957975.
      1868174.99       13957175.
#Sta/Elev= 30
  3970.7 1921.58  4119.4  1901.6  4332.6  1854.6  4390.5  1844.5  4536.9 1835.44
  4574.7 1829.66  4611.3 1829.91  4668.9 1821.94  4764.6 1808.69  4810.1 1807.52
  4840.1 1808.49  4884.2 1800.04    4911 1789.03  4977.4 1779.38  4978.9 1778.38
  5051.7 1779.38  5061.1  1783.6  5130.9 1789.44  5295.7 1797.35  6393.7 1803.29
  6538.4 1805.69  6584.9 1817.11  6608.2 1826.06  6620.4 1834.36  6683.4 1867.55
  6740.9 1907.92  6816.8 1953.66  6839.4 1963.83  6871.5 1968.52    6970 1967.95
#Mann= 9 ,-1 , 0
  3970.7      .1       0  4332.6    .035       0  4668.9     .07       0
  4810.1      .1       0  4884.2     .07       0  4977.4     .05       0
  5051.7     .07       0  6393.7    .035       0  6620.4      .1       0
Bank Sta=4977.4,5051.7
XS Rating Curve= 0 ,0
Exp/Cntr=0.3,0.1

Type RM Length L Ch R = 1 ,43712   ,702,702,702
BEGIN DESCRIPTION:
Johnson Creek 44.0
END DESCRIPTION:
XS GIS Cut Line= 3
      1871075.02     13958325.02        1870075.       13957325.
      1868420.51     13957110.42
#Sta/Elev= 30
  3586.3 1925.46  3770.2 1893.48  3852.2 1871.01  3897.5 1855.81    3954 1855.06
  4012.8 1847.54  4157.6 1835.36  4251.3 1828.56  4606.1  1816.9  4766.4 1810.88
  4830.8 1814.18    4845 1811.42  4887.4 1787.43  4901.6 1783.72  4973.5 1779.22
    4975 1778.22  5047.8 1779.22  5090.4  1780.7  5144.6  1787.1  5243.6 1793.86
  5639.6 1800.29  5708.1 1800.14  5936.7 1799.95    6209 1803.01  6351.8  1803.7
  6410.2 1817.46    6503 1861.53  6603.9 1922.73  6644.2 1941.54  6668.9 1948.28
#Mann= 17 ,-1 , 0
  3586.3    .035       0  3852.2    .063       0  4012.8    .035       0
  4157.6      .1       0  4251.3     .07       0  4606.1      .1       0
  4766.4     .07       0  4973.5     .05       0  5047.8     .07       0
  5090.4    .035       0  5144.6     .07       0  5243.6    .035       0
  5639.6     .07       0  5708.1    .035       0  5936.7      .1       0
    6209    .035       0  6410.2      .1       0
Bank Sta=4973.5,5047.8
XS Rating Curve= 0 ,0
Exp/Cntr=0.3,0.1

Type RM Length L Ch R = 1 ,43010   ,702,702,702
BEGIN DESCRIPTION:
Johnson Creek 43.0
END DESCRIPTION:
XS GIS Cut Line= 3
      1870524.99     13957174.98        1870125.       13956675.
        1869725.       13956175.
#Sta/Elev= 30
  4359.7 1810.93  4715.9 1799.37  4765.5 1795.16  4807.9    1786  4922.4 1780.45
  4926.8 1777.37  4928.3 1776.37  5001.2 1777.37  5050.4 1778.17  5056.8 1782.36
  5071.2 1784.99  5077.6 1788.99    5092  1790.6  5256.1 1794.57  5311.7 1793.94
  5412.2 1794.72  5426.6 1798.85  5447.7 1810.18  5455.4 1816.27    5505 1844.35
  5519.4 1856.39  5554.7 1876.41  5562.7 1883.79  5569.1  1886.5  5583.5 1901.22
  5589.9 1904.27  5597.9 1911.94  5604.3 1914.56  5612.3 1921.41  5640.3 1931.62
#Mann= 5 ,-1 , 0
  4359.7     .07       0  4926.8     .05       0  5001.2     .07       0
  5311.7    .035       0  5447.7      .1       0
Bank Sta=4926.8,5001.2
XS Rating Curve= 0 ,0
Exp/Cntr=0.3,0.1

Type RM Length L Ch R = 1 ,42308   ,488,488,488
BEGIN DESCRIPTION:
Johnson Creek 42.0
END DESCRIPTION:
XS GIS Cut Line= 3
        1871625.     13958075.01        1870425.       13956075.
      1869924.99       13956075.
#Sta/Elev= 30
    2663 1948.01  2793.2 1942.94  2931.2 1929.61  3005.1 1917.19  3120.2 1891.01
  3174.2 1876.74  3195.6 1864.14  3238.3  1864.6  3281.1 1854.11  3339.4 1845.64
  3488.8 1834.24  3691.9  1813.6  3932.2 1803.37  4536.7 1796.27  4620.4 1791.74
  4727.2 1787.81  4744.3 1784.04  4944.9 1781.35  4981.8 1779.78  4988.2 1776.69
  4989.7 1775.69  5062.6 1776.69  5075.4 1784.56  5133.8 1789.56  5155.4  1793.2
  5275.4 1827.58  5325.4  1851.1  5395.4 1878.38  5405.4 1886.61  5495.4  1909.2
#Mann= 9 ,-1 , 0
    2663      .1       0  3120.2    .035       0  3488.8      .1       0
  3691.9     .07       0  4620.4    .035       0  4744.3     .07       0
  4988.2     .05       0  5062.6     .07       0  5133.8      .1       0
Bank Sta=4988.2,5062.6
XS Rating Curve= 0 ,0
Exp/Cntr=0.3,0.1