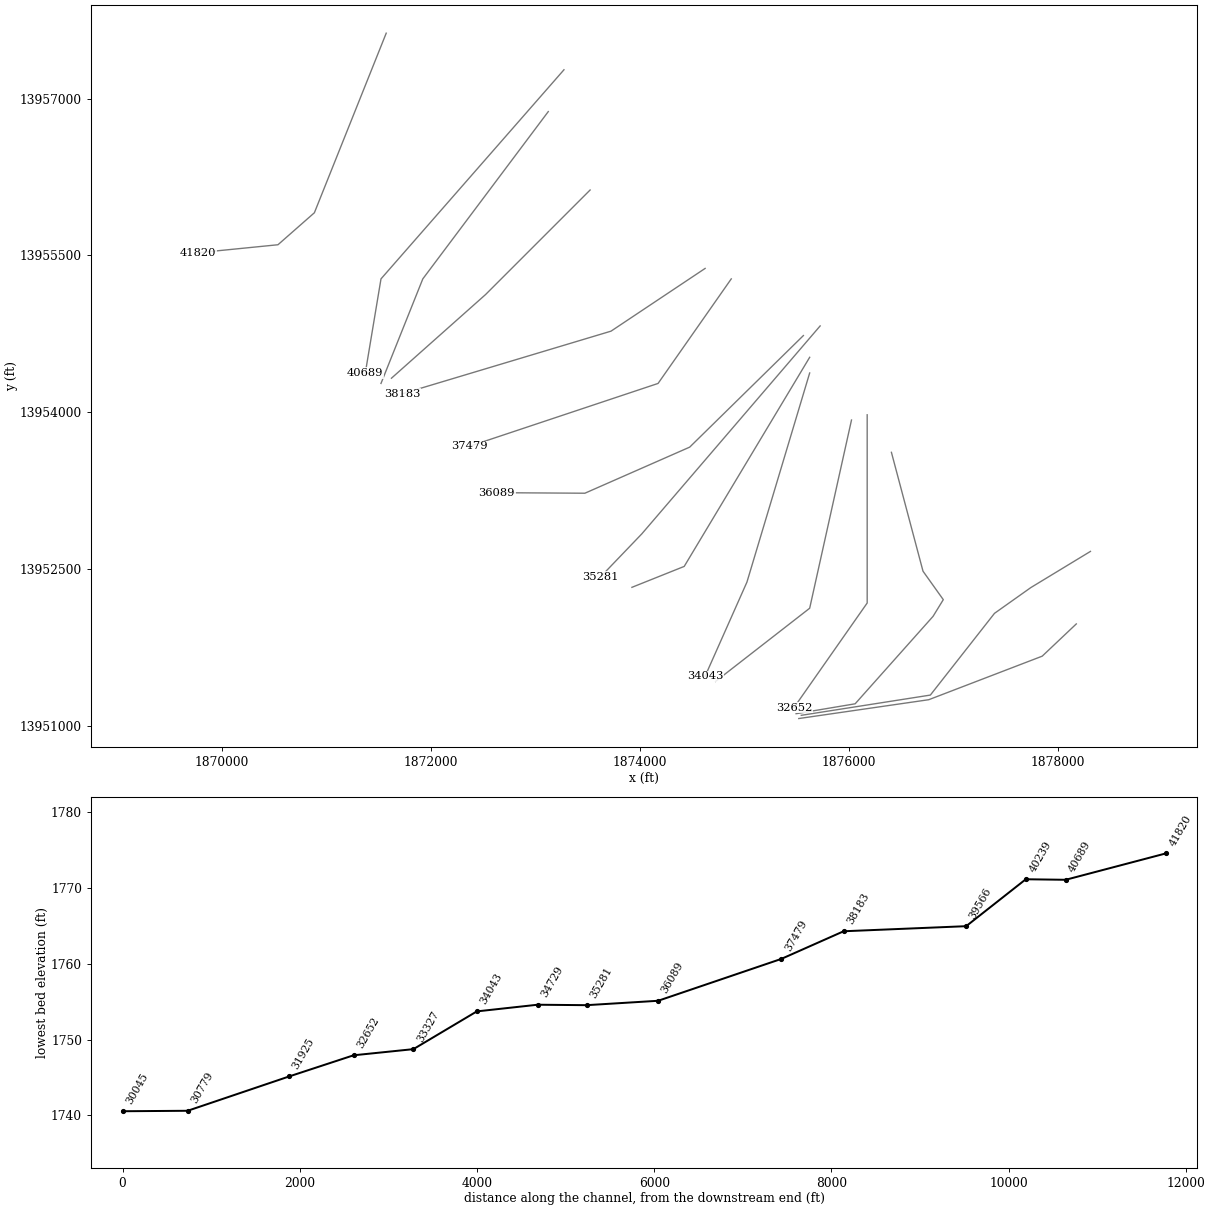
HEC-RAS study Johnson Creek.prj: Johnson Creek Base Level Engineering

--- Johnson Creek.g01 (geometry) --- (continued)

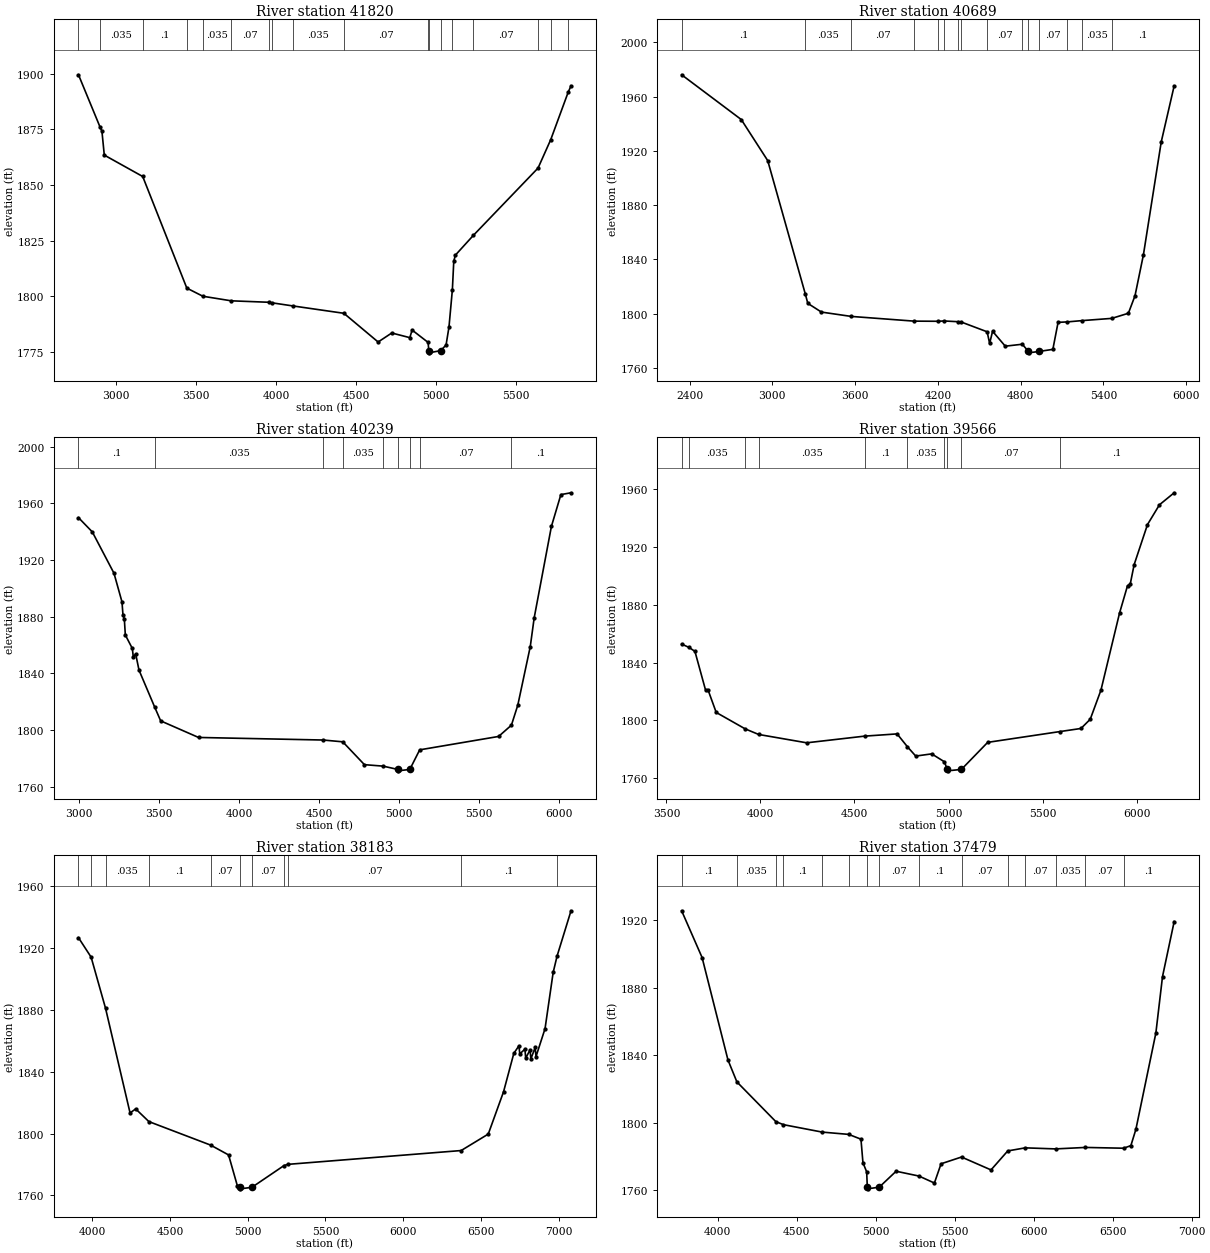
Type RM Length L Ch R = 1 ,41820   ,1131,1131,1131
BEGIN DESCRIPTION:
Johnson Creek 41.0
END DESCRIPTION:
XS GIS Cut Line= 4
      1871574.99     13957624.98        1870888.     13955907.51
      1870539.62     13955601.46      1869775.02       13955525.
#Sta/Elev= 30
  2763.2 1899.56  2897.8 1876.12  2909.9 1874.21  2924.7 1863.45  3165.1 1853.83
  3441.1 1803.65  3541.6 1799.99  3718.7 1797.94    3953 1797.29  3973.9 1797.04
  4102.5 1795.66  4423.8 1792.33  4638.2 1779.42  4723.4 1783.47  4836.5 1781.38
  4850.8  1784.8    4951 1779.23    4955 1775.55  4956.5 1774.55  5029.4 1775.55
  5063.3 1778.07  5081.5 1786.16  5102.8 1802.95  5111.5 1815.73  5121.5 1818.47
  5234.2 1827.37  5638.8 1857.62  5718.2 1870.39  5826.9 1891.63  5845.1  1894.6
#Mann= 18 ,-1 , 0
  2763.2      .1       0  2897.8    .035       0  3165.1      .1       0
  3441.1     .07       0  3541.6    .035       0  3718.7     .07       0
    3953    .035       0  3973.9     .07       0  4102.5    .035       0
  4423.8     .07       0    4951      .1       0    4955     .05       0
  5029.4      .1       0  5102.8    .035       0  5234.2     .07       0
  5638.8      .1       0  5718.2     .07       0  5826.9      .1       0
Bank Sta=4955,5029.4
XS Rating Curve= 0 ,0
Exp/Cntr=0.3,0.1

Type RM Length L Ch R = 1 ,40689   ,450,450,450
BEGIN DESCRIPTION:
Johnson Creek 40.0
END DESCRIPTION:
XS GIS Cut Line= 3
      1873274.99     13957274.99      1871525.05     13955275.03
        1871375.     13954375.02
#Sta/Elev= 30
  2342.4 1976.03  2774.7 1943.02  2966.4 1912.75  3238.4 1814.59  3256.9 1807.54
  3355.6 1801.11  3571.5 1797.92    4027 1794.44  4203.3 1794.33  4243.7 1794.57
  4347.7 1794.01  4368.5  1793.8  4556.8 1786.58  4574.7 1777.99  4596.1 1786.97
  4688.1 1775.98  4811.8 1777.42    4856 1772.07  4857.5 1771.07  4931.2 1772.07
    5033 1773.63  5070.9 1793.54  5137.8 1793.88  5243.2 1794.81  5460.1 1796.47
  5580.4 1800.24  5628.5 1813.17  5689.3 1843.25  5818.6 1926.58  5912.3 1967.88
#Mann= 15 ,-1 , 0
  2342.4      .1       0  3238.4    .035       0  3571.5     .07       0
    4027    .035       0  4203.3      .1       0  4243.7     .07       0
  4347.7      .1       0  4368.5    .035       0  4556.8     .07       0
  4811.8    .094       0    4856     .05       0  4931.2     .07       0
  5137.8     .07       0  5243.2    .035       0  5460.1      .1       0
Bank Sta=4856,4931.2
XS Rating Curve= 0 ,0
Exp/Cntr=0.3,0.1

Type RM Length L Ch R = 1 ,40239   ,673,673,673
BEGIN DESCRIPTION:
Johnson Creek 39.0
END DESCRIPTION:
XS GIS Cut Line= 3
      1873124.97     13956874.96        1871925.       13955275.
        1871525.     13954274.99
#Sta/Elev= 30
  2995.9 1949.97  3082.3  1939.9  3217.7  1910.7  3267.7 1890.46    3274 1881.07
  3282.3 1878.46  3288.6 1867.09  3332.3 1857.57  3338.6  1851.4  3353.1 1853.78
    3374 1842.28  3470.9 1816.44  3509.4 1806.43  3745.9 1794.72  4525.3  1792.9
    4647 1791.63  4782.3  1775.5    4899 1774.47  4990.6 1772.14  4992.1 1771.14
  5065.8 1772.14  5127.6 1785.97  5620.5 1795.43  5700.6 1803.39  5740.4 1817.52
  5818.4 1858.94  5842.7 1879.13  5950.4 1943.77  6009.6 1966.26  6072.9 1967.54
#Mann= 9 ,-1 , 0
  2995.9      .1       0  3470.9    .035       0  4525.3     .07       0
    4647    .035       0    4899     .07       0  4990.6     .05       0
  5065.8     .07       0  5127.6     .07       0  5700.6      .1       0
Bank Sta=4990.6,5065.8
XS Rating Curve= 0 ,0
Exp/Cntr=0.3,0.1

Type RM Length L Ch R = 1 ,39566   ,1383,1383,1383
BEGIN DESCRIPTION:
Johnson Creek 38.0
END DESCRIPTION:
XS GIS Cut Line= 3
        1873525.       13956125.        1872525.       13955125.
      1871624.98     13954324.98
#Sta/Elev= 30
  3581.1 1852.83  3621.2 1850.45  3651.8 1847.74  3708.4 1820.85  3722.5 1820.66
  3764.9 1805.43  3919.2 1794.02  3990.5 1790.17  4245.8 1784.38  4553.9 1789.01
  4726.6 1790.56  4781.4 1781.64  4825.6 1775.19  4910.5 1776.71  4977.8 1771.25
  4993.3 1765.95  4994.8 1764.95  5068.5 1765.95  5208.1 1784.69  5591.1 1792.15
    5704 1794.32  5753.3  1800.7  5810.2 1820.88  5908.9 1874.22  5951.5 1893.29
  5965.7 1894.24  5986.7 1907.88  6057.7 1935.68  6121.3 1949.38  6199.5  1957.7
#Mann= 10 ,-1 , 0
  3581.1      .1       0  3621.2    .035       0  3919.2     .07       0
  3990.5    .035       0  4553.9      .1       0  4781.4    .035       0
  4977.8     .07       0  4993.3     .05       0  5068.5     .07       0
  5591.1      .1       0
Bank Sta=4993.3,5068.5
XS Rating Curve= 0 ,0
Exp/Cntr=0.3,0.1

Type RM Length L Ch R = 1 ,38183   ,704,704,704
BEGIN DESCRIPTION:
Johnson Creek 37.0
END DESCRIPTION:
XS GIS Cut Line= 3
      1874624.97     13955374.98        1873725.       13954775.
      1871724.99       13954175.
#Sta/Elev= 30
  3910.6  1926.8  3991.9 1914.21  4084.8  1881.1  4242.6 1813.38  4278.6 1816.01
  4363.8 1807.79    4761 1792.58  4876.5 1786.22  4933.6 1766.06  4951.4 1765.28
  4952.9 1764.28    5027 1765.28    5233 1779.32  5257.5 1780.12  6373.3 1789.06
  6547.8 1799.72  6646.1 1827.09  6712.3 1851.95  6745.3 1856.87  6750.5 1851.61
  6783.6 1854.64  6788.8 1848.86  6816.7 1854.22  6821.9 1848.37  6849.7 1855.75
  6854.9 1849.84  6913.2 1867.96  6965.4 1904.31  6990.8 1914.98  7080.3 1944.21
#Mann= 11 ,-1 , 0
  3910.6     .07       0  3991.9      .1       0  4084.8    .035       0
  4363.8      .1       0    4761     .07       0  4951.4     .05       0
    5027     .07       0    5233      .1       0  5257.5     .07       0
  6373.3      .1       0  6990.8     .07       0
Bank Sta=4951.4,5027
XS Rating Curve= 0 ,0
Exp/Cntr=0.3,0.1

Type RM Length L Ch R = 1 ,37479   ,1390,1390,1390
BEGIN DESCRIPTION:
Johnson Creek 36.0
END DESCRIPTION:
XS GIS Cut Line= 3
      1874874.99     13955274.99        1874175.       13954275.
      1872375.01       13953675.
#Sta/Elev= 30
  3771.3 1925.66  3900.8 1897.91  4064.7 1837.08  4121.1  1824.1  4367.9  1800.5
  4415.8 1798.72  4661.4  1794.3  4828.6 1792.95  4906.5 1790.11  4919.1 1776.16
  4942.7 1770.69  4946.7 1761.63  4948.2 1760.63  5022.3 1761.63    5129 1771.07
  5273.7 1768.22  5371.4 1764.08  5413.6  1775.5    5543 1779.51  5729.8 1771.86
  5835.7 1783.13  5946.5 1784.96  6138.1 1784.33  6327.7  1785.2  6569.5 1784.74
  6615.2 1786.28  6646.9 1795.92  6773.4 1853.08  6815.5 1886.62  6889.3 1919.25
#Mann= 15 ,-1 , 0
  3771.3      .1       0  4121.1    .035       0  4367.9     .07       0
  4415.8      .1       0  4661.4    .035       0  4828.6     .07       0
  4946.7     .05       0  5022.3     .07       0  5273.7      .1       0
    5543     .07       0  5835.7    .035       0  5946.5     .07       0
  6138.1    .035       0  6327.7     .07       0  6569.5      .1       0
Bank Sta=4946.7,5022.3
XS Rating Curve= 0 ,0
Exp/Cntr=0.3,0.1

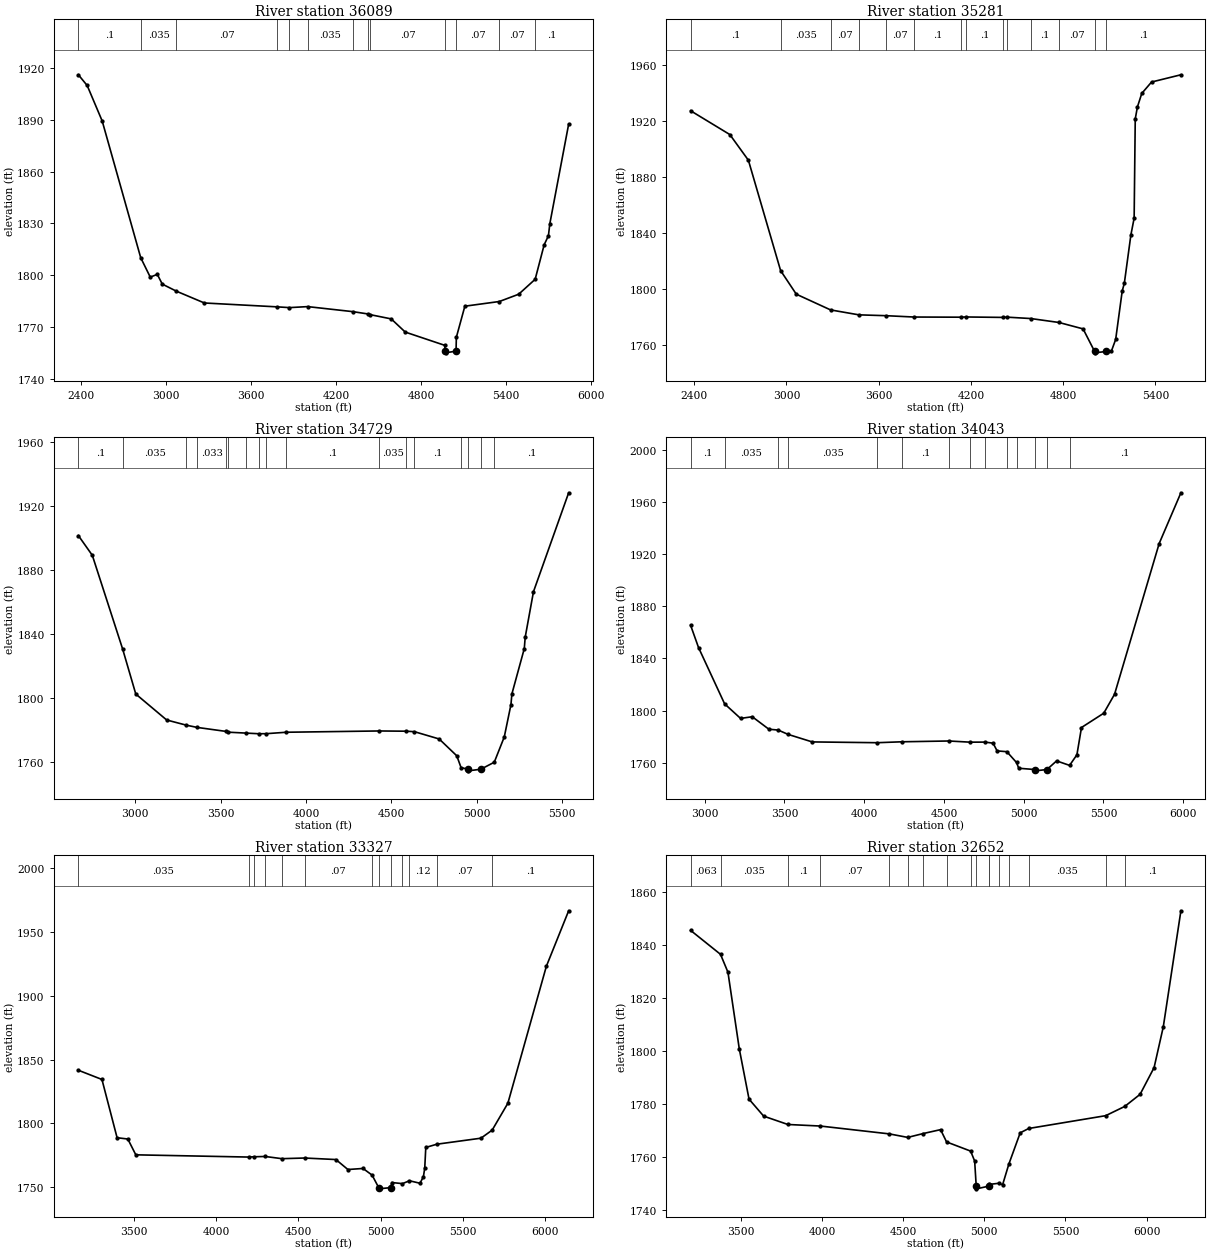
Type RM Length L Ch R = 1 ,36089   ,808,808,808
BEGIN DESCRIPTION:
Johnson Creek 35.0
END DESCRIPTION:
XS GIS Cut Line= 4
      1875564.97     13954732.93      1874477.56     13953665.88
        1873475.       13953225.      1872632.13     13953230.12
#Sta/Elev= 30
  2380.9 1915.95  2443.1 1909.75  2549.1 1889.22  2821.2 1810.12  2888.5  1798.9
  2938.1 1800.51  2973.4 1794.86  3073.6 1790.75  3270.4 1783.95  3781.3 1781.72
  3871.4 1781.27  3999.9 1781.85  4318.5 1778.94  4424.7 1777.61  4441.7 1777.19
  4589.8 1774.74  4688.7 1767.12  4967.3 1759.46  4971.8 1756.11  4973.3 1755.11
  5047.4 1756.11  5049.6 1764.12  5109.6 1782.09  5352.9  1784.8  5489.6 1789.01
    5606 1797.66  5669.6 1817.63  5699.6 1822.84  5709.6 1829.84  5842.5 1887.41
#Mann= 13 ,-1 , 0
  2380.9      .1       0  2821.2    .035       0  3073.6     .07       0
  3781.3      .1       0  3871.4     .07       0  3999.9    .035       0
  4318.5     .07       0  4424.7    .035       0  4441.7     .07       0
  4971.8     .05       0  5047.4     .07       0  5352.9     .07       0
    5606      .1       0
Bank Sta=4971.8,5047.4
XS Rating Curve= 0 ,0
Exp/Cntr=0.3,0.1

Type RM Length L Ch R = 1 ,35281   ,552,552,552
BEGIN DESCRIPTION:
Johnson Creek 34.0
END DESCRIPTION:
XS GIS Cut Line= 3
      1875725.03     13954825.03      1874019.04     13952835.77
      1873625.01     13952425.01
#Sta/Elev= 30
  2376.3 1927.36  2631.5 1910.36  2752.2 1892.04  2961.8 1813.25  3063.9  1796.4
  3286.8 1785.18  3471.2 1781.65  3645.5 1781.06  3831.1 1780.09  4135.2 1779.98
  4165.9 1780.14  4410.4 1779.82  4432.3 1780.02  4589.2 1779.02    4773  1776.2
  4929.7 1771.63  5004.8 1755.53  5006.3 1754.53  5080.5 1755.53  5113.4 1755.61
  5141.7 1764.09  5184.2 1798.61  5198.3 1804.35  5240.8 1838.78  5261.9 1850.69
  5269.1 1921.56  5283.2 1930.07  5311.5 1939.72  5375.1 1947.87  5566.1 1953.04
#Mann= 14 ,-1 , 0
  2376.3      .1       0  2961.8    .035       0  3286.8     .07       0
  3471.2    .033       0  3645.5     .07       0  3831.1      .1       0
  4135.2     .07       0  4165.9      .1       0  4410.4    .035       0
  4432.3     .07       0  4589.2      .1       0    4773     .07       0
  5004.8     .05       0  5080.5      .1       0
Bank Sta=5004.8,5080.5
XS Rating Curve= 0 ,0
Exp/Cntr=0.3,0.1

Type RM Length L Ch R = 1 ,34729   ,686,686,686
BEGIN DESCRIPTION:
Johnson Creek 33.0
END DESCRIPTION:
XS GIS Cut Line= 3
        1875625.     13954524.99        1874425.       13952525.
      1873924.99       13952325.
#Sta/Elev= 30
  2667.6 1901.38  2749.2 1889.08  2926.8  1830.6  3003.8 1802.51  3184.6 1786.32
  3300.5 1783.06  3362.3  1781.7  3534.4 1779.16  3544.2 1778.71  3651.3 1778.13
    3726 1777.73  3768.2 1777.78  3885.2 1778.67  4428.6 1779.47  4586.8 1779.32
  4635.4 1779.02  4780.3 1774.47  4883.4 1763.97  4908.3 1756.64  4948.5 1755.59
    4950 1754.59  5024.2 1755.59  5102.9 1759.96  5161.5 1775.74  5200.6 1795.95
    5206 1802.55  5278.7 1830.89    5284 1837.96  5332.5 1866.38  5538.5 1928.08
#Mann= 17 ,-1 , 0
  2667.6      .1       0  2926.8    .035       0  3300.5     .07       0
  3362.3    .033       0  3534.4     .07       0  3544.2    .033       0
  3651.3     .07       0    3726    .033       0  3768.2     .07       0
  3885.2      .1       0  4428.6    .035       0  4586.8     .07       0
  4635.4      .1       0  4908.3    .033       0  4948.5    .033       0
  5024.2    .033       0  5102.9      .1       0
Bank Sta=4948.5,5024.2
XS Rating Curve= 0 ,0
Exp/Cntr=0.3,0.1

Type RM Length L Ch R = 1 ,34043   ,716,716,716
BEGIN DESCRIPTION:
Johnson Creek 32.0
END DESCRIPTION:
XS GIS Cut Line= 3
        1875625.     13954375.01        1875025.       13952375.
      1874624.98     13951474.96
#Sta/Elev= 30
  2912.2 1865.41  2961.8 1848.35  3125.4 1805.11  3225.4 1793.94  3298.5 1795.24
  3402.9 1785.64  3461.2 1785.01  3522.9 1781.69  3674.3 1775.91  4080.9  1775.3
  4237.9 1776.01  4530.8 1776.62  4663.2 1775.72  4757.7 1775.76    4808 1774.95
  4833.2 1769.02  4894.4  1768.4  4954.8 1760.12  4968.9  1755.7  5069.8 1754.71
  5071.3 1753.71  5145.5 1754.71  5206.1 1761.34  5287.5  1757.9  5333.4 1766.02
  5362.1 1786.96  5501.6 1797.94  5569.3 1812.46    5849 1928.18  5985.2 1967.12
#Mann= 14 ,-1 , 0
  2912.2      .1       0  3125.4    .035       0  3461.2     .07       0
  3522.9    .035       0  4080.9     .07       0  4237.9      .1       0
  4530.8     .07       0  4663.2    .035       0  4757.7     .07       0
  4894.4    .035       0  4954.8     .07       0  5069.8     .05       0
  5145.5     .07       0  5287.5      .1       0
Bank Sta=5069.8,5145.5
XS Rating Curve= 0 ,0
Exp/Cntr=0.3,0.1

Type RM Length L Ch R = 1 ,33327   ,675,675,675
BEGIN DESCRIPTION:
Johnson Creek 31.0
END DESCRIPTION:
XS GIS Cut Line= 3
      1876025.01     13953925.04        1875625.       13952125.
      1874725.02     13951425.02
#Sta/Elev= 30
  3160.9 1841.62  3304.4  1834.4  3396.6 1788.76  3461.9 1787.75  3510.5 1775.37
  4196.6 1773.62  4227.5 1773.84    4298 1774.08  4399.5 1772.36  4537.9 1772.87
  4728.3 1771.68  4801.3 1763.87  4893.5 1764.69  4948.6 1759.47  4988.7 1749.73
  4990.2 1748.73  5064.4 1749.73  5068.2 1753.67  5133.6 1752.82  5175.9 1755.06
  5240.1 1753.11  5260.9 1758.21  5269.1 1765.03  5275.4 1781.16    5343  1783.7
  5611.1  1788.4  5679.4 1794.72  5774.9 1815.75  6009.3 1923.08    6145 1966.54
#Mann= 13 ,-1 , 0
  3160.9    .035       0  4196.6     .07       0  4227.5    .035       0
    4298     .07       0  4399.5    .035       0  4537.9     .07       0
  4948.6    .035       0  4988.7    .035       0  5064.4    .035       0
  5133.6     .07       0  5175.9     .12       0    5343     .07       0
  5679.4      .1       0
Bank Sta=4988.7,5064.4
XS Rating Curve= 0 ,0
Exp/Cntr=0.3,0.1

Type RM Length L Ch R = 1 ,32652   ,727,727,727
BEGIN DESCRIPTION:
Johnson Creek 30.0
END DESCRIPTION:
XS GIS Cut Line= 3
        1876175.     13953974.99        1876175.       13952175.
      1875475.03     13951175.04
#Sta/Elev= 30
  3190.8 1845.67    3375 1836.61  3420.8 1829.85  3490.8 1800.82  3550.8 1781.83
  3640.8 1775.42  3789.9 1772.26  3990.1 1771.67  4415.3  1768.7  4528.5 1767.37
  4623.8 1768.83  4730.8 1770.31  4767.7 1765.66    4916 1762.19  4940.8 1758.43
  4950.4 1748.92  4951.9 1747.92  5026.1 1748.92  5028.5 1749.58  5090.5 1750.03
  5112.9 1749.45  5151.3 1757.26  5221.4 1769.11  5274.1 1770.75    5748 1775.59
  5865.5 1779.09  5959.9 1783.66  6046.2 1793.77  6102.9 1809.19  6211.4 1853.08
#Mann= 17 ,-1 , 0
  3190.8    .063       0    3375    .035       0  3789.9      .1       0
  3990.1     .07       0  4415.3      .1       0  4528.5    .035       0
  4623.8     .07       0  4767.7    .035       0    4916     .07       0
  4950.4     .05       0  5026.1     .07       0  5028.5    .035       0
  5090.5     .07       0  5151.3     .12       0  5274.1    .035       0
    5748     .07       0  5865.5      .1       0
Bank Sta=4950.4,5026.1
XS Rating Curve= 0 ,0
Exp/Cntr=0.3,0.1

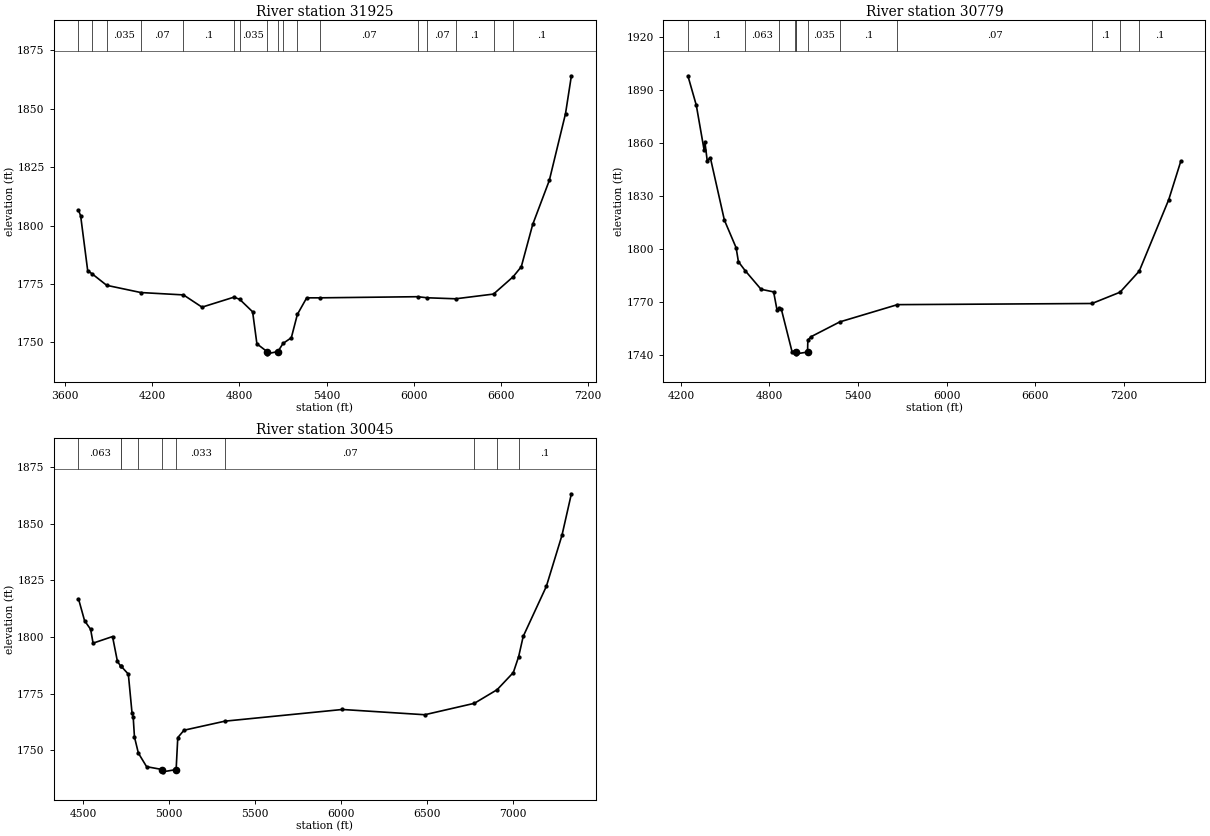
Type RM Length L Ch R = 1 ,31925   ,1146,1146,1146
BEGIN DESCRIPTION:
Johnson Creek 29.1
END DESCRIPTION:
XS GIS Cut Line= 6
      1876406.77     13953616.21      1876708.93     13952479.16
      1876902.94     13952207.02      1876804.84     13952047.19
      1876059.95      13951211.1       1875495.2     13951116.32
#Sta/Elev= 30
  3693.8 1806.57  3708.5  1804.2  3757.1  1780.7  3786.2 1779.42  3887.8 1774.44
  4122.8 1771.35  4415.9 1770.34  4543.5  1765.1  4762.9 1769.37  4802.1 1768.48
  4891.6 1763.12  4921.1 1749.41  4990.2 1746.13  4991.7 1745.13  5065.9 1746.13
  5100.6 1749.57  5157.9 1752.01  5199.5    1762  5263.6 1769.09  5356.1 1769.09
  6026.8 1769.57  6093.1 1769.11  6288.9 1768.68  6548.9  1770.7  6683.4 1778.08
  6739.9 1782.39  6818.3 1800.46  6932.6  1819.3  7044.1 1847.88  7084.5 1864.08
#Mann= 17 ,-1 , 0
  3693.8    .035       0  3786.2    .063       0  3887.8    .035       0
  4122.8     .07       0  4415.9      .1       0  4762.9     .07       0
  4802.1    .035       0  4990.2    .035       0  5065.9    .035       0
  5100.6    .033       0  5199.5      .1       0  5356.1     .07       0
  6026.8    .035       0  6093.1     .07       0  6288.9      .1       0
  6548.9    .035       0  6683.4      .1       0
Bank Sta=4990.2,5065.9
XS Rating Curve= 0 ,0
Exp/Cntr=0.3,0.1

Type RM Length L Ch R = 1 ,30779   ,734,734,734
BEGIN DESCRIPTION:
Johnson Creek 29.2
END DESCRIPTION:
XS GIS Cut Line= 5
      1878310.33     13952668.63      1877739.82     13952322.41
      1877392.53     13952076.16      1876779.23     13951294.47
      1875544.75     13951100.97
#Sta/Elev= 30
  4247.8 1898.18  4304.8 1881.47  4357.1 1856.36    4363 1860.64  4378.5 1850.11
  4399.8 1851.75  4494.8 1816.39  4574.3 1800.72  4589.8  1792.8  4635.2 1787.78
  4742.9 1777.19  4828.2  1775.7  4850.6  1765.7  4861.5 1766.37  4880.5 1765.85
  4952.8 1741.83  4970.7 1742.04  4977.4 1741.67  4978.3  1741.6  4979.8  1740.6
  5057.7  1741.6  5059.8 1748.31  5080.7 1750.28  5275.7 1758.69  5666.4 1768.48
    6983 1769.13    7173 1775.53  7303.1 1787.51  7502.8 1828.04    7584  1849.7
#Mann= 12 ,-1 , 0
  4247.8      .1       0  4635.2    .063       0  4861.5      .1       0
  4970.7     .07       0  4977.4    .035       0  4978.3    .035       0
  5057.7    .035       0  5275.7      .1       0  5666.4     .07       0
    6983      .1       0    7173    .035       0  7303.1      .1       0
Bank Sta=4978.3,5057.7
XS Rating Curve= 0 ,0
Exp/Cntr=0.3,0.1

Type RM Length L Ch R = 1 ,30045   ,894,894,894
BEGIN DESCRIPTION:
Johnson Creek 29.0
END DESCRIPTION:
XS GIS Cut Line= 4
        1878175.       13951975.      1877848.98      13951666.6
      1876763.84     13951250.17       1875520.8     13951070.07
#Sta/Elev= 30
  4472.4 1816.86  4507.8  1807.2    4543  1803.4  4557.2 1797.31  4670.4 1800.22
  4698.7 1789.31  4716.9 1787.25  4719.2 1787.24  4762.3 1783.64  4783.7 1766.56
  4790.6 1764.71  4797.9 1755.92  4820.7  1748.8  4868.6 1742.81  4960.9 1741.54
  4962.4 1740.54  5040.3 1741.54  5049.9 1755.64  5086.1  1758.9  5324.4  1762.9
  6007.3 1768.05  6486.5 1765.73  6775.1 1770.77  6907.6 1776.78  7001.8 1784.35
  7032.8 1791.39  7059.2 1800.28  7193.8 1822.35  7284.7 1844.88  7339.5 1863.21
#Mann= 10 ,-1 , 0
  4472.4    .063       0  4716.9    .033       0  4719.2      .1       0
  4820.7    .033       0  4960.9    .033       0  5040.3    .033       0
  5324.4     .07       0  6775.1      .1       0  6907.6    .035       0
  7032.8      .1       0
Bank Sta=4960.9,5040.3
XS Rating Curve= 0 ,0
Exp/Cntr=0.3,0.1