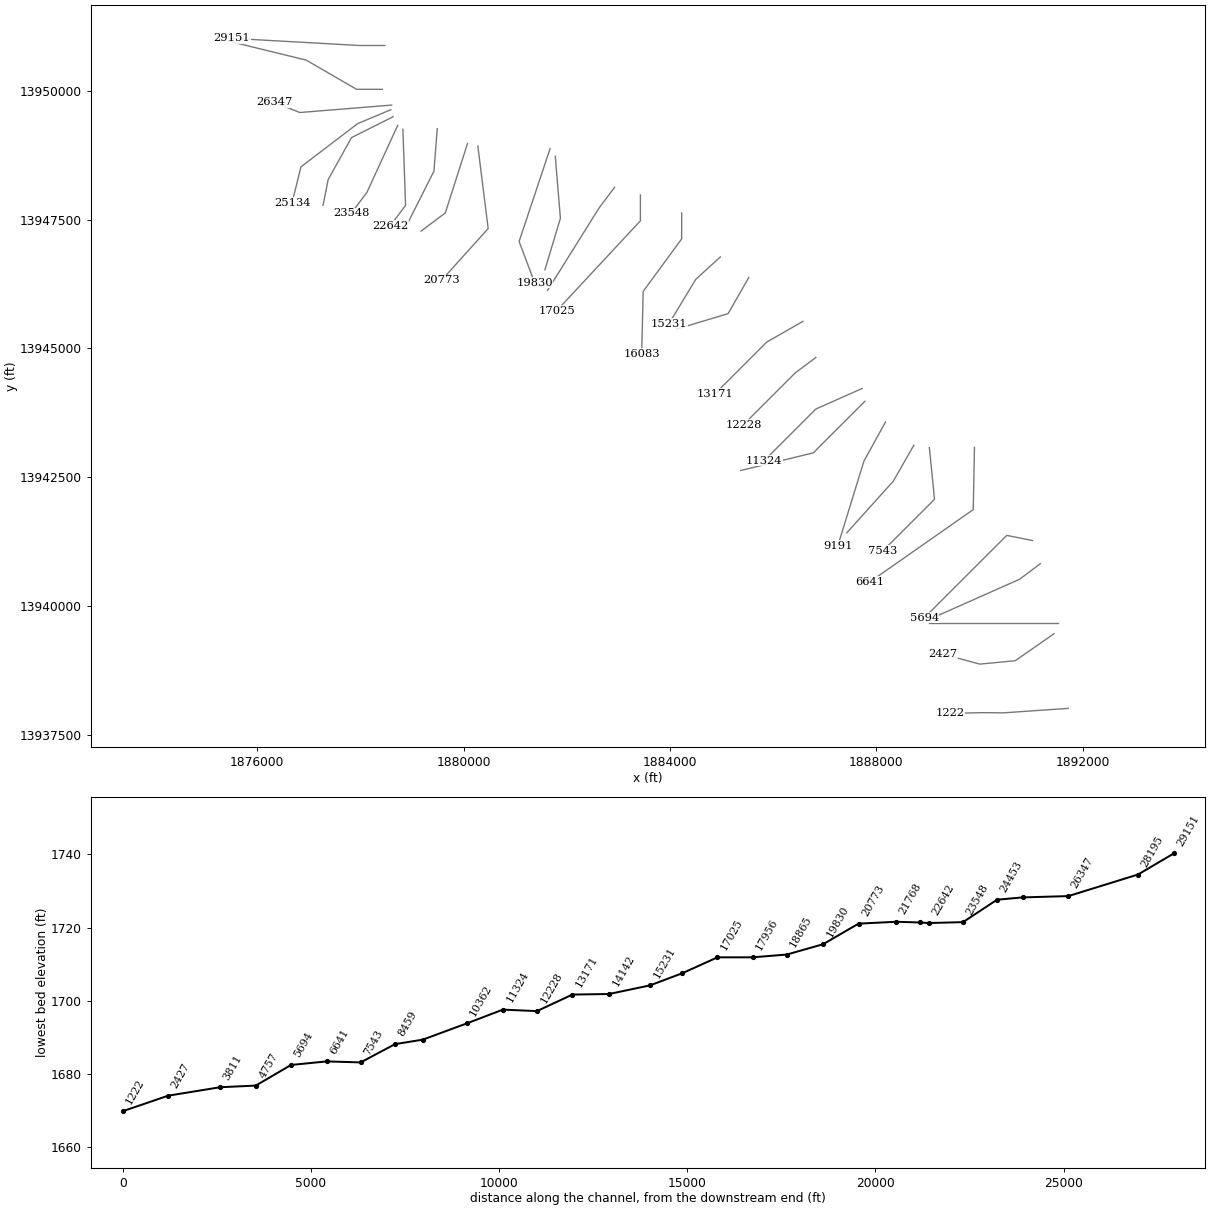
HEC-RAS study Johnson Creek.prj: Johnson Creek Base Level Engineering

--- Johnson Creek.g01 (geometry) --- (continued)

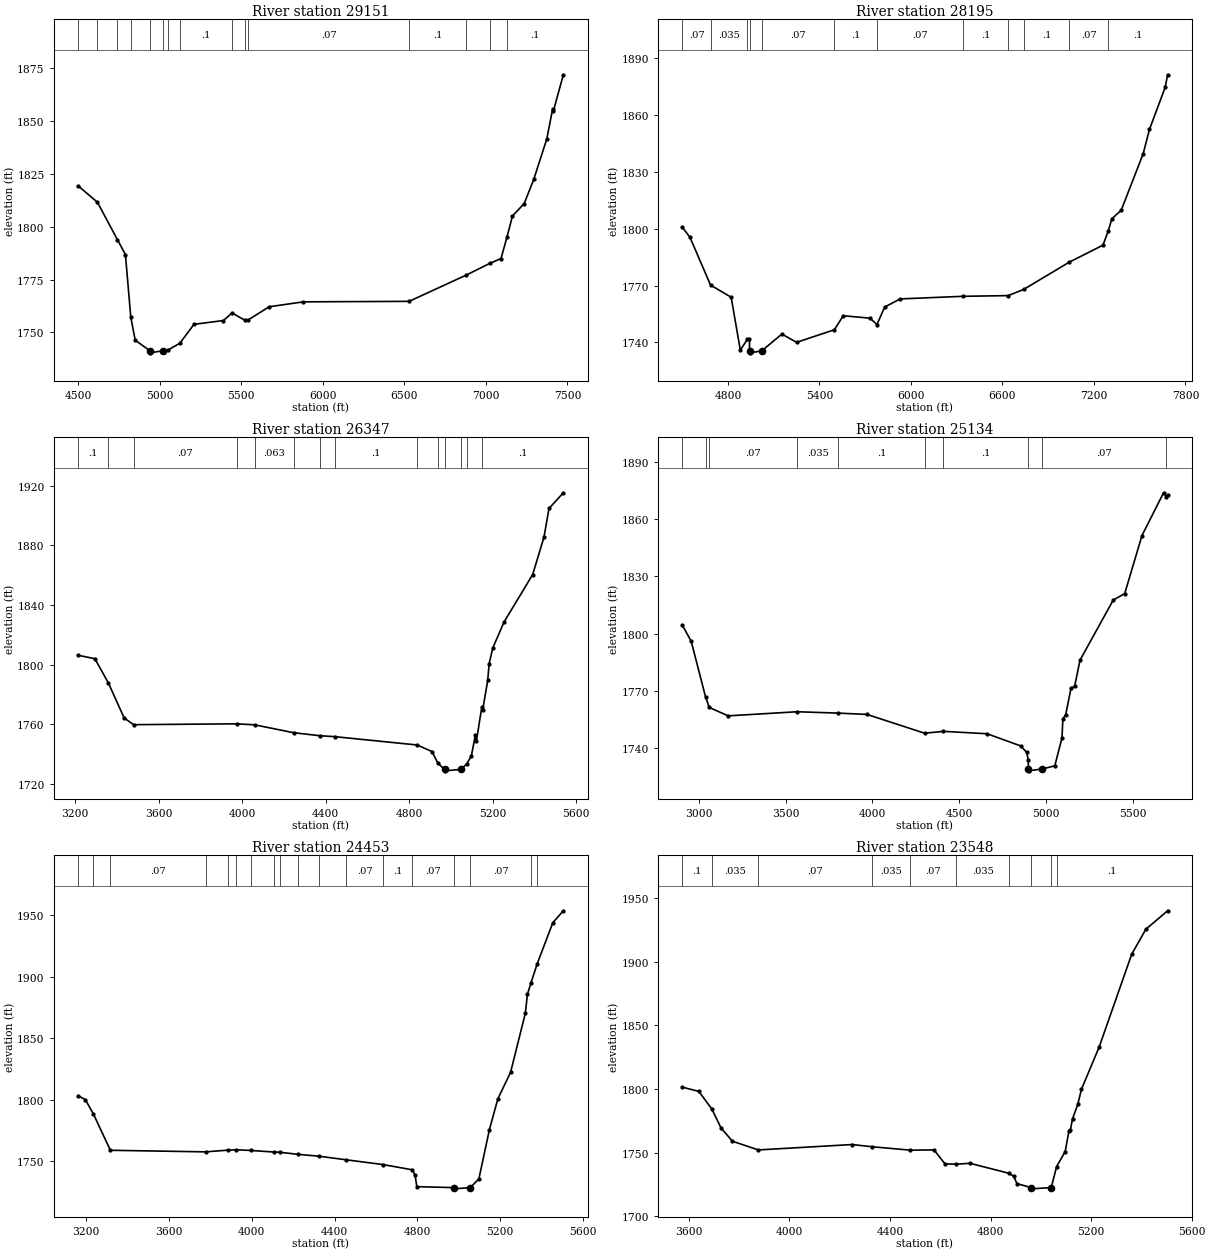
Type RM Length L Ch R = 1 ,29151   ,956,956,956
BEGIN DESCRIPTION:
Johnson Creek 28.0
END DESCRIPTION:
XS GIS Cut Line= 3
      1878475.04       13950875.        1877975.       13950875.
      1875503.72     13951013.63
#Sta/Elev= 30
    4500 1819.35  4618.3 1811.59  4740.8 1793.89    4790 1786.83    4823 1757.17
    4850 1746.27  4940.3 1741.28  4941.8 1740.28  5019.7 1741.28  5053.2 1741.68
  5123.9 1744.85  5210.4 1753.78  5390.6 1755.57  5444.1 1759.15  5523.4 1755.68
  5540.3 1755.73  5671.1 1762.09  5881.4 1764.42  6529.6 1764.66    6881 1777.14
  7024.3 1782.63  7093.3 1784.94  7130.1 1795.24  7163.4 1805.09  7235.2 1810.96
  7293.6 1822.35  7373.8 1841.56  7409.6 1855.73  7414.6 1854.92  7475.2 1871.93
#Mann= 15 ,-1 , 0
    4500    .035       0  4618.3      .1       0  4740.8     .07       0
    4823    .094       0  4940.3     .05       0  5019.7    .094       0
  5053.2    .094       0  5123.9      .1       0  5444.1     .07       0
  5523.4      .1       0  5540.3     .07       0  6529.6      .1       0
    6881     .07       0  7024.3    .035       0  7130.1      .1       0
Bank Sta=4940.3,5019.7
XS Rating Curve= 0 ,0
Exp/Cntr=0.3,0.1

Type RM Length L Ch R = 1 ,28195   ,1848,1848,1848
BEGIN DESCRIPTION:
Johnson Creek 27.0
END DESCRIPTION:
XS GIS Cut Line= 4
      1878424.99       13950025.        1877925.       13950025.
      1876948.37     13950591.52      1875439.53     13950961.15
#Sta/Elev= 30
  4500.7 1800.73  4550.7 1795.41  4685.4 1770.23  4820.7 1763.81  4880.7 1735.91
  4926.3 1741.56  4940.7 1741.75    4941 1735.49  4942.5 1734.49  5020.4 1735.49
  5153.5  1744.4  5249.5 1740.03  5497.7 1746.67  5555.6 1754.07  5731.5 1752.78
  5776.9  1749.4  5827.5 1758.66  5929.4 1762.95  6342.3 1764.32  6637.6 1764.69
  6739.9 1767.99  7037.3  1782.3  7259.3 1791.31  7294.6 1798.94  7317.2 1805.21
    7379 1809.75  7523.1 1839.59  7564.3  1852.4  7667.3  1874.6  7683.2 1881.22
#Mann= 12 ,-1 , 0
  4500.7     .07       0  4685.4    .035       0  4926.3     .07       0
    4941     .05       0  5020.4     .07       0  5497.7      .1       0
  5776.9     .07       0  6342.3      .1       0  6637.6     .07       0
  6739.9      .1       0  7037.3     .07       0  7294.6      .1       0
Bank Sta=4941,5020.4
XS Rating Curve= 0 ,0
Exp/Cntr=0.3,0.1

Type RM Length L Ch R = 1 ,26347   ,1213,1213,1213
BEGIN DESCRIPTION:
Johnson Creek 26.0
END DESCRIPTION:
XS GIS Cut Line= 3
      1878604.89     13949719.33        1876825.       13949575.
      1876325.04     13949774.98
#Sta/Elev= 30
  3214.3 1806.22  3294.5 1803.95  3359.5 1787.57  3434.9  1764.1  3480.2 1759.61
  3974.2 1760.18  4059.6 1759.52    4246 1754.23  4371.5 1752.19    4443 1751.57
  4839.4 1745.95  4909.7 1741.51  4938.1  1733.6  4969.7  1729.6  4971.2  1728.6
  5049.2  1729.6  5076.7 1733.42  5098.3 1738.78  5117.2 1752.68  5122.5 1748.85
  5147.7 1771.25  5152.2 1769.49  5176.4 1789.45  5183.1 1800.57  5200.6 1811.12
  5254.5 1828.59  5391.8 1860.48  5445.7 1885.55  5469.9 1904.84  5538.5 1915.39
#Mann= 14 ,-1 , 0
  3214.3      .1       0  3359.5    .035       0  3480.2     .07       0
  3974.2    .035       0  4059.6    .063       0    4246    .035       0
  4371.5     .07       0    4443      .1       0  4839.4    .035       0
  4938.1    .094       0  4969.7     .05       0  5049.2    .094       0
  5076.7    .063       0  5147.7      .1       0
Bank Sta=4969.7,5049.2
XS Rating Curve= 0 ,0
Exp/Cntr=0.3,0.1

Type RM Length L Ch R = 1 ,25134   ,681,681,681
BEGIN DESCRIPTION:
Johnson Creek 25.0
END DESCRIPTION:
XS GIS Cut Line= 4
      1878588.03     13949629.07      1877944.36      13949358.8
      1876846.89     13948520.41        1876675.     13947825.01
#Sta/Elev= 30
  2905.7 1804.45  2956.4 1796.09  3039.7 1766.78  3060.5 1761.42  3169.3 1757.03
  3567.2 1759.18    3804 1758.46  3969.2 1757.77  4301.2 1747.94  4409.5 1748.91
  4661.2 1747.66  4854.4 1741.29  4889.8  1737.9    4898 1734.07  4899.7 1729.24
  4901.2 1728.24  4979.7 1729.24  5051.2 1730.86  5092.6  1745.4  5097.8 1755.47
  5114.1 1757.65    5145 1771.63  5165.6 1772.47  5196.5 1786.19  5387.8 1817.61
    5454 1821.04  5553.6 1851.43  5677.9 1873.81  5692.5 1871.79  5701.2 1872.68
#Mann= 10 ,-1 , 0
  2905.7      .1       0  3039.7    .035       0  3060.5     .07       0
  3567.2    .035       0    3804      .1       0  4301.2     .07       0
  4409.5      .1       0  4899.7     .05       0  4979.7     .07       0
  5692.5    .035       0
Bank Sta=4899.7,4979.7
XS Rating Curve= 0 ,0
Exp/Cntr=0.3,0.1

Type RM Length L Ch R = 1 ,24453   ,905,905,905
BEGIN DESCRIPTION:
Johnson Creek 24.0
END DESCRIPTION:
XS GIS Cut Line= 4
      1878633.85     13949494.07      1877826.99     13949088.59
        1877375.       13948275.        1877275.     13947775.02
#Sta/Elev= 30
  3161.4  1803.2    3196 1800.15  3234.4  1788.7  3317.2 1758.93  3777.3 1757.65
  3885.9 1759.05  3925.5 1759.34  3994.5 1758.79  4109.9 1757.49  4134.3 1757.34
  4224.4 1755.63  4326.2 1754.08  4453.5 1751.26  4635.3  1747.3  4774.9 1743.09
  4789.2 1738.66  4797.2 1729.38  4975.5 1728.61    4977 1727.61  5055.5 1728.61
  5097.1  1735.7  5148.1 1775.77  5188.9 1800.81  5250.1 1822.19  5321.5 1870.28
  5331.7 1885.69  5348.6 1894.86    5379 1910.51    5454 1943.71    5505 1953.46
#Mann= 18 ,-1 , 0
  3161.4      .1       0  3234.4    .035       0  3317.2     .07       0
  3777.3    .035       0  3885.9     .07       0  3925.5    .035       0
  3994.5     .07       0  4109.9    .035       0  4134.3     .07       0
  4224.4    .035       0  4326.2    .063       0  4453.5     .07       0
  4635.3      .1       0  4774.9     .07       0  4975.5     .05       0
  5055.5     .07       0  5348.6    .035       0    5379      .1       0
Bank Sta=4975.5,5055.5
XS Rating Curve= 0 ,0
Exp/Cntr=0.3,0.1

Type RM Length L Ch R = 1 ,23548   ,906,906,906
BEGIN DESCRIPTION:
Johnson Creek 23.0
END DESCRIPTION:
XS GIS Cut Line= 3
      1878721.37     13949324.57        1878125.       13948025.
      1877824.98     13947624.98
#Sta/Elev= 30
  3574.4 1801.43  3639.9 1798.09  3691.8 1784.15    3728 1769.37  3773.5 1758.91
  3876.5 1752.07  4249.8 1756.31  4329.5 1754.56  4481.4 1751.88  4575.2  1752.1
  4619.2 1741.03  4664.2 1740.87  4718.2 1741.55  4874.5 1733.65  4892.6 1731.18
  4905.2 1725.57  4961.5 1722.47    4963 1721.47  5041.5 1722.47  5062.9 1738.98
    5097 1750.82  5111.6 1766.77  5117.8 1767.93  5126.1 1776.53    5147 1787.88
  5161.6 1799.75  5232.4 1833.16  5361.6 1906.04  5417.8 1925.61  5504.3 1940.15
#Mann= 10 ,-1 , 0
  3574.4      .1       0  3691.8    .035       0  3876.5     .07       0
  4329.5    .035       0  4481.4     .07       0  4664.2    .035       0
  4874.5     .07       0  4961.5     .05       0  5041.5     .07       0
  5062.9      .1       0
Bank Sta=4961.5,5041.5
XS Rating Curve= 0 ,0
Exp/Cntr=0.3,0.1

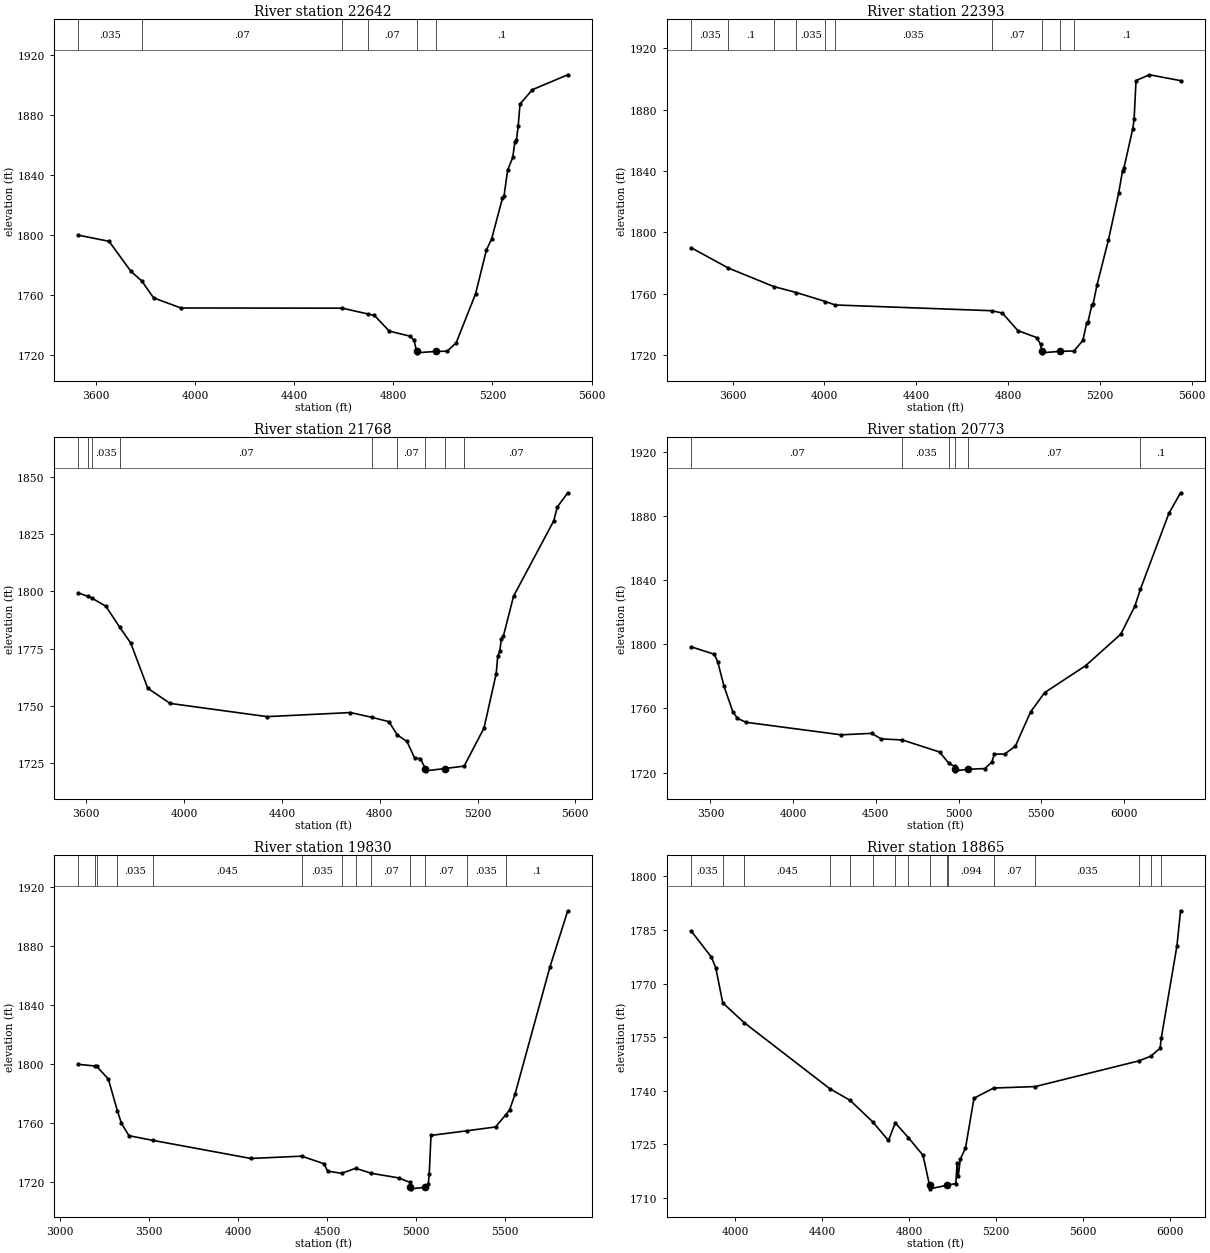
Type RM Length L Ch R = 1 ,22642   ,249,249,249
BEGIN DESCRIPTION:
Johnson Creek 22.0
END DESCRIPTION:
XS GIS Cut Line= 3
      1878822.32     13949248.83        1878875.       13947775.
      1878574.98     13947374.97
#Sta/Elev= 30
  3529.4 1799.64  3653.3 1795.55  3741.4 1775.57  3785.6 1769.08  3833.4 1757.82
  3943.5 1751.12  4593.9 1750.99  4697.4 1747.15    4724 1746.16    4784  1735.7
  4866.6 1732.39  4884.1 1729.69  4894.1 1722.23  4895.6 1721.23  4974.2 1722.23
  5017.7  1722.3  5054.2 1727.96  5132.3 1760.62    5176 1789.79  5196.9 1797.09
  5240.6 1824.21  5246.9 1825.55  5261.5 1842.95  5282.3 1851.47  5290.6 1861.59
  5296.9 1862.88  5304.2 1872.41  5311.5    1887  5361.5 1896.58  5504.2 1906.51
#Mann= 6 ,-1 , 0
  3529.4    .035       0  3785.6     .07       0  4593.9    .035       0
  4697.4     .07       0  4894.1     .05       0  4974.2      .1       0
Bank Sta=4894.1,4974.2
XS Rating Curve= 0 ,0
Exp/Cntr=0.3,0.1

Type RM Length L Ch R = 1 ,22393   ,625,625,625
BEGIN DESCRIPTION:
Johnson Creek 21.1
END DESCRIPTION:
XS GIS Cut Line= 3
      1879488.46      13949262.2      1879424.97     13948439.95
      1878837.81     13947271.71
#Sta/Elev= 30
  3419.5 1789.94  3581.7 1776.67  3779.4 1764.62  3878.3 1760.69  4004.7 1754.84
  4046.6  1752.6  4729.2 1748.85  4775.8 1747.29  4842.9 1735.91  4925.1 1731.32
  4941.8 1726.96  4946.4 1722.38  4947.9 1721.38  5026.5 1722.38  5087.3 1722.59
    5126 1729.45  5142.8 1740.78  5148.3 1741.51  5165.1 1752.35  5170.7 1753.11
  5187.4 1765.41  5237.7 1795.09  5282.3 1825.68    5299 1840.13  5304.6 1841.63
  5343.7  1867.6  5349.3 1873.54  5357.8 1898.95  5416.3  1902.7  5551.7 1898.88
#Mann= 10 ,-1 , 0
  3419.5    .035       0  3581.7      .1       0  3779.4     .07       0
  3878.3    .035       0  4004.7     .07       0  4046.6    .035       0
  4729.2     .07       0  4946.4     .05       0  5026.5     .07       0
  5087.3      .1       0
Bank Sta=4946.4,5026.5
XS Rating Curve= 0 ,0
Exp/Cntr=0.3,0.1

Type RM Length L Ch R = 1 ,21768   ,995,995,995
BEGIN DESCRIPTION:
Johnson Creek 21.0
END DESCRIPTION:
XS GIS Cut Line= 3
      1880074.99     13948974.97      1879644.52     13947628.19
      1879175.03     13947275.02
#Sta/Elev= 30
  3567.6 1799.36  3605.6 1797.89  3621.8 1797.17  3680.2 1793.54  3736.6  1784.4
  3781.9 1777.43  3851.5  1757.7  3942.8 1751.05  4339.3 1745.27  4680.4 1747.05
  4767.6 1744.98  4837.9 1743.05  4871.9 1737.27  4911.4 1734.42  4942.9 1727.16
  4966.3 1726.91  4986.5 1722.57    4988 1721.57  5066.6 1722.57  5145.3 1723.65
  5226.5 1740.28  5276.4 1764.09  5282.7 1771.76    5291 1773.76  5297.3  1779.3
  5305.6  1780.4  5347.3 1797.92  5511.8 1830.89  5526.3 1836.93    5569 1843.14
#Mann= 9 ,-1 , 0
  3567.6    .035       0  3605.6     .07       0  3621.8    .035       0
  3736.6     .07       0  4767.6    .035       0  4871.9     .07       0
  4986.5     .05       0  5066.6     .07       0  5145.3     .07       0
Bank Sta=4986.5,5066.6
XS Rating Curve= 0 ,0
Exp/Cntr=0.3,0.1

Type RM Length L Ch R = 1 ,20773   ,943,943,943
BEGIN DESCRIPTION:
Johnson Creek 20.0
END DESCRIPTION:
XS GIS Cut Line= 3
        1880275.     13948924.97        1880475.       13947325.
      1879574.99     13946324.99
#Sta/Elev= 30
  3383.5 1798.44  3524.6 1793.76  3544.7 1788.95  3582.5 1773.77  3635.4 1758.05
  3663.1 1753.79    3716 1751.34  4290.5 1743.53  4474.4 1744.44  4532.3    1741
  4660.7  1740.3  4885.1 1732.81  4942.1 1725.66  4975.8 1723.81  4977.1 1722.06
  4978.6 1721.06  5057.3 1722.06  5158.5 1722.47  5201.1  1726.5  5215.3 1731.46
  5278.8 1731.55  5343.1 1736.45    5435 1757.78  5520.2 1769.87  5767.6 1786.65
  5979.9 1806.27  6065.1 1823.72  6098.6 1834.31  6270.7 1881.61  6341.3 1894.51
#Mann= 6 ,-1 , 0
  3383.5     .07       0  4660.7    .035       0  4942.1     .07       0
  4977.1     .05       0  5057.3     .07       0  6098.6      .1       0
Bank Sta=4977.1,5057.3
XS Rating Curve= 0 ,0
Exp/Cntr=0.3,0.1

Type RM Length L Ch R = 1 ,19830   ,965,965,965
BEGIN DESCRIPTION:
Johnson Creek 19.0
END DESCRIPTION:
XS GIS Cut Line= 3
        1881675.     13948874.99        1881075.       13947075.
      1881375.02     13946274.96
#Sta/Elev= 30
  3102.4  1799.9  3196.7 1798.76  3205.8  1798.5    3271 1789.96  3321.8 1768.45
  3344.8 1759.85    3387 1751.47  3520.2 1748.34  4072.2 1736.03  4358.4  1737.6
  4483.2 1732.46  4504.3  1727.4  4582.9 1725.97  4661.7 1729.35  4749.8 1725.96
  4904.9 1722.81  4968.1 1719.73  4969.4 1716.42  4970.9 1715.42  5049.7 1716.42
  5070.1 1718.85  5075.4 1725.56  5085.2 1751.67  5287.4 1754.81  5448.3 1757.41
  5506.2 1765.76  5527.5 1769.07  5557.8  1779.7  5753.6  1865.8  5854.2 1904.08
#Mann= 13 ,-1 , 0
  3102.4     .07       0  3196.7    .035       0  3205.8     .07       0
  3321.8    .035       0  3520.2    .045       0  4358.4    .035       0
  4582.9     .07       0  4661.7    .035       0  4749.8     .07       0
  4969.4     .05       0  5049.7     .07       0  5287.4    .035       0
  5506.2      .1       0
Bank Sta=4969.4,5049.7
XS Rating Curve= 0 ,0
Exp/Cntr=0.3,0.1

Type RM Length L Ch R = 1 ,18865   ,909,909,909
BEGIN DESCRIPTION:
Johnson Creek 18.0
END DESCRIPTION:
XS GIS Cut Line= 3
      1881775.29     13948727.84        1881875.       13947525.
        1881575.     13946524.99
#Sta/Elev= 30
  3797.6 1784.72  3890.8 1777.39  3910.8 1774.46  3943.3 1764.58  4041.7 1759.06
  4435.4  1740.6  4529.1 1737.33  4632.3 1731.36  4705.3 1726.12  4736.7 1731.06
  4796.5 1726.93  4864.1 1721.99  4894.2  1713.6  4895.7  1712.6  4974.5  1713.6
    4981 1713.67    5015 1714.09  5021.1 1719.77  5026.3 1716.18  5035.9 1720.92
  5059.4 1723.92  5098.5 1737.93  5188.7 1740.78  5380.2 1741.19  5856.4 1748.37
  5911.3 1749.67  5954.6 1751.91    5960 1754.75  6032.1 1780.57  6048.6 1790.34
#Mann= 16 ,-1 , 0
  3797.6    .035       0  3943.3     .07       0  4041.7    .045       0
  4435.4    .035       0  4529.1     .07       0  4632.3      .1       0
  4736.7     .07       0  4796.5      .1       0  4894.2     .05       0
  4974.5      .1       0    4981    .094       0  5188.7     .07       0
  5380.2    .035       0  5856.4     .07       0  5911.3    .035       0
    5960      .1       0
Bank Sta=4894.2,4974.5
XS Rating Curve= 0 ,0
Exp/Cntr=0.3,0.1

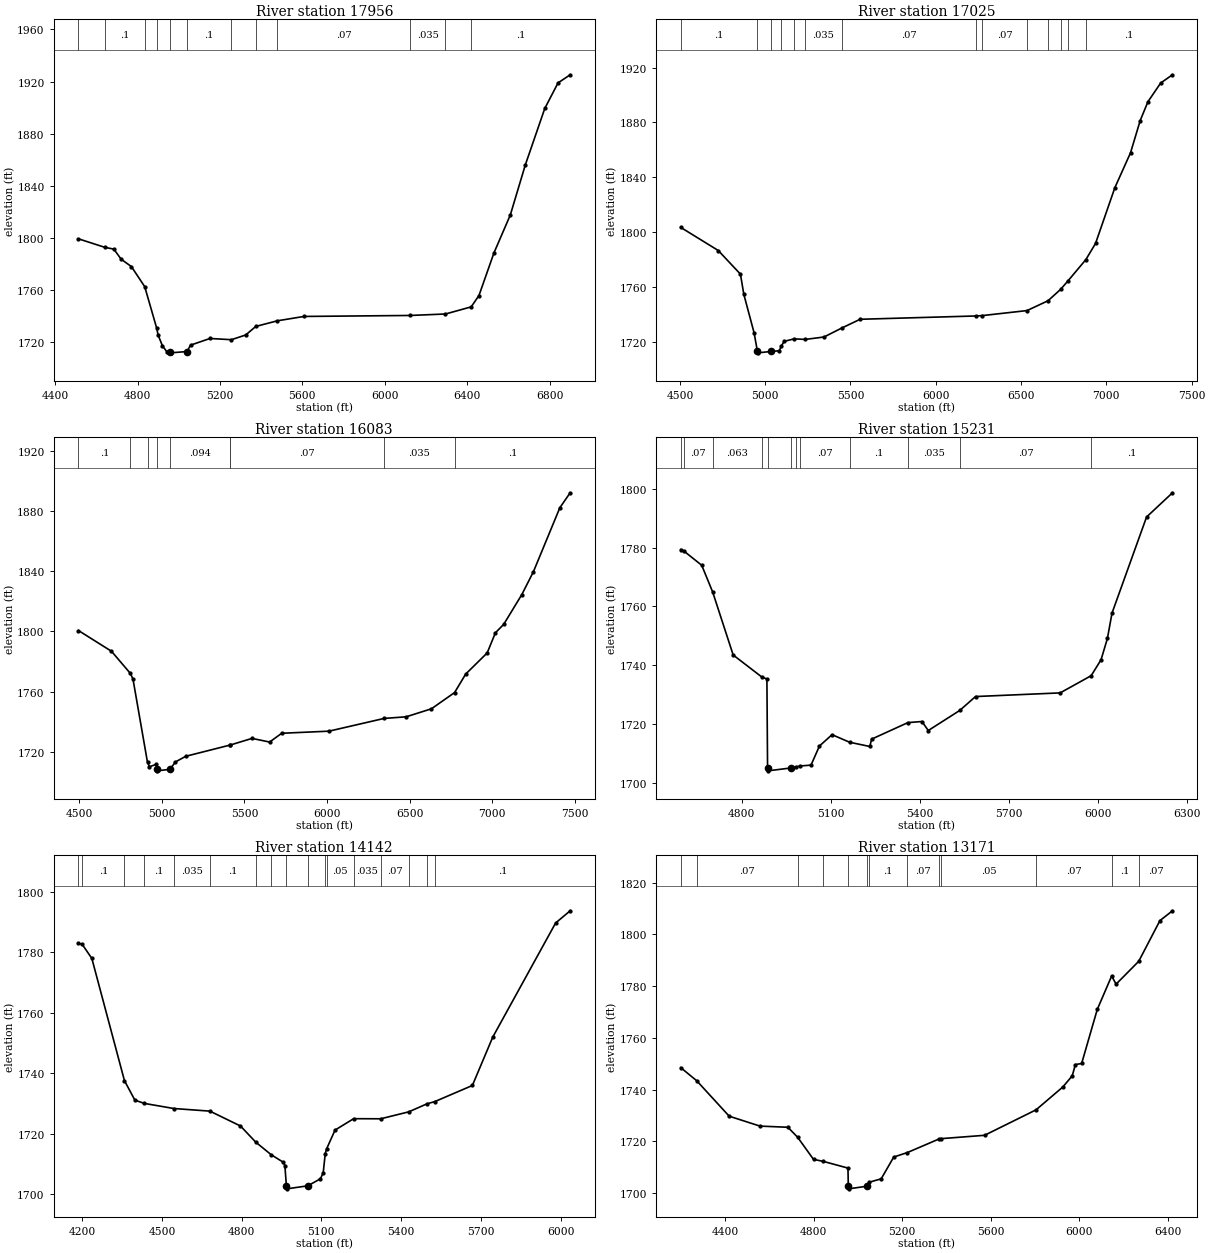
Type RM Length L Ch R = 1 ,17956   ,931,931,931
BEGIN DESCRIPTION:
Johnson Creek 17.0
END DESCRIPTION:
XS GIS Cut Line= 3
      1882924.98     13948124.98        1882625.       13947725.
      1881624.98     13946124.97
#Sta/Elev= 30
  4513.2 1799.32  4641.1 1792.78    4685 1791.41  4720.5 1783.68  4770.5 1777.97
  4834.9 1762.61  4892.9 1730.83  4899.6 1725.64  4920.5 1717.36  4941.3 1712.84
  4959.4 1712.84  4960.9 1711.84  5039.9 1712.84  5057.4 1717.74  5151.7 1722.86
  5255.6 1721.92  5325.1 1725.54    5374  1732.1  5479.1 1736.43  5608.1 1739.76
    6122 1740.51  6294.7 1741.64  6419.4  1747.1  6457.2 1755.79  6530.3 1788.63
  6609.3 1817.56  6682.4 1856.09  6776.7 1899.33    6841 1918.91    6900 1925.16
#Mann= 12 ,-1 , 0
  4513.2     .07       0  4641.1      .1       0  4834.9     .07       0
  4892.9      .1       0  4959.4     .05       0  5039.9      .1       0
  5255.6     .07       0    5374    .035       0  5479.1     .07       0
    6122    .035       0  6294.7     .07       0  6419.4      .1       0
Bank Sta=4959.4,5039.9
XS Rating Curve= 0 ,0
Exp/Cntr=0.3,0.1

Type RM Length L Ch R = 1 ,17025   ,942,942,942
BEGIN DESCRIPTION:
Johnson Creek 16.0
END DESCRIPTION:
XS GIS Cut Line= 3
        1883425.     13947974.99        1883425.       13947475.
      1881802.16     13945730.38
#Sta/Elev= 30
  4504.8 1803.36  4724.8  1786.5  4854.8 1769.26  4874.8 1754.46  4934.8 1726.48
  4954.5 1712.84    4956 1711.84    5035 1712.84  5082.7 1713.38  5094.3 1716.69
  5111.1 1720.22  5170.8 1722.06  5234.2 1721.62  5344.6 1723.39  5447.7 1729.87
  5556.6 1736.33  6237.1 1738.75    6273 1739.02  6534.7 1742.67  6657.6 1749.81
  6731.6 1758.13  6776.7 1764.59  6879.5 1779.81  6936.4 1791.62  7049.8 1832.35
  7141.6  1857.8  7198.3  1881.3  7243.8 1895.07  7318.5 1908.71  7387.5 1914.71
#Mann= 14 ,-1 , 0
  4504.8      .1       0  4954.5     .05       0    5035      .1       0
  5094.3      .1       0  5170.8     .07       0  5234.2    .035       0
  5447.7     .07       0  6237.1    .035       0    6273     .07       0
  6534.7    .035       0  6657.6     .07       0  6731.6      .1       0
  6776.7     .07       0  6879.5      .1       0
Bank Sta=4954.5,5035
XS Rating Curve= 0 ,0
Exp/Cntr=0.3,0.1

Type RM Length L Ch R = 1 ,16083   ,852,852,852
BEGIN DESCRIPTION:
Johnson Creek 15.0
END DESCRIPTION:
XS GIS Cut Line= 4
        1884225.     13947624.96        1884225.       13947125.
      1883478.77     13946106.39      1883450.18     13944892.49
#Sta/Elev= 30
  4495.3  1800.6  4695.3 1786.82  4809.2 1772.18  4825.3 1768.46  4913.4 1713.05
  4925.3  1710.2  4965.3 1711.71  4968.5 1708.46    4970 1707.46  5049.1 1708.46
    5082 1713.33  5144.6 1717.11  5412.6 1724.55  5412.9 1724.55    5546 1728.99
  5652.6 1726.57  5725.9  1732.4  6011.8 1733.79  6345.8 1742.25  6479.4 1743.33
  6632.4 1748.65  6772.5 1759.43  6839.5 1771.67  6969.6 1785.71  7019.6  1799.1
  7069.6 1804.66  7179.6 1824.48  7249.6 1839.63  7409.7  1882.1  7472.2 1892.02
#Mann= 9 ,-1 , 0
  4495.3      .1       0  4809.2    .035       0  4913.4    .094       0
  4968.5     .05       0  5049.1    .094       0  5412.6    .035       0
  5412.9     .07       0  6345.8    .035       0  6772.5      .1       0
Bank Sta=4968.5,5049.1
XS Rating Curve= 0 ,0
Exp/Cntr=0.3,0.1

Type RM Length L Ch R = 1 ,15231   ,1089,1089,1089
BEGIN DESCRIPTION:
Johnson Creek 14.0
END DESCRIPTION:
XS GIS Cut Line= 3
      1884975.04     13946775.03      1884499.25     13946341.67
      1883974.98     13945474.97
#Sta/Elev= 30
  4594.3 1779.32  4604.9 1778.81    4665 1773.97  4701.7 1764.95    4771  1743.5
    4868 1735.98  4884.6 1735.35  4886.8 1705.16  4888.3 1704.16  4967.4 1705.16
  4981.5 1705.48  4997.5 1705.82  5033.2  1706.1  5061.6  1712.6  5104.1 1716.44
    5163 1713.88  5231.2 1712.43  5237.4 1714.93  5359.6 1720.54  5406.9 1720.91
  5428.2 1717.85  5534.2 1724.67  5587.3 1729.39  5872.5 1730.63  5976.9 1736.47
  6010.2 1741.88  6031.6 1749.11  6047.1 1757.71  6163.5 1790.36  6250.8 1798.59
#Mann= 12 ,-1 , 0
  4594.3    .035       0  4604.9     .07       0  4701.7    .063       0
    4868    .094       0  4886.8     .05       0  4967.4    .094       0
  4981.5    .063       0  4997.5     .07       0    5163      .1       0
  5359.6    .035       0  5534.2     .07       0  5976.9      .1       0
Bank Sta=4886.8,4967.4
XS Rating Curve= 0 ,0
Exp/Cntr=0.3,0.1

Type RM Length L Ch R = 1 ,14142   ,971,971,971
BEGIN DESCRIPTION:
Johnson Creek 13.0
END DESCRIPTION:
XS GIS Cut Line= 3
      1885524.99     13946374.98        1885125.       13945675.
      1884125.04     13945375.01
#Sta/Elev= 30
    4186 1783.03  4200.3 1782.65  4236.4 1778.01  4359.1 1737.58  4398.3 1731.14
  4433.7 1730.06  4544.7 1728.37  4680.7  1727.5  4795.7 1722.58  4853.3 1717.23
  4911.5 1713.07  4956.9 1710.59  4962.7  1709.5  4968.4  1702.8  4969.9  1701.8
  5049.1  1702.8  5096.6 1705.13    5107 1707.15  5114.6 1713.42  5119.4 1714.95
  5151.4 1721.23  5221.4    1725  5323.3 1724.97    5429 1727.27  5497.7 1729.93
  5527.2 1730.67  5668.2 1735.99  5744.8 1751.97  5981.4 1789.73  6036.2 1793.77
#Mann= 17 ,-1 , 0
    4186     .07       0  4200.3      .1       0  4359.1     .07       0
  4433.7      .1       0  4544.7    .035       0  4680.7      .1       0
  4853.3    .035       0  4911.5    .094       0  4968.4     .05       0
  5049.1    .094       0  5114.6     .07       0  5119.4     .05       0
  5221.4    .035       0  5323.3     .07       0    5429    .035       0
  5497.7     .07       0  5527.2      .1       0
Bank Sta=4968.4,5049.1
XS Rating Curve= 0 ,0
Exp/Cntr=0.3,0.1

Type RM Length L Ch R = 1 ,13171   ,943,943,943
BEGIN DESCRIPTION:
Johnson Creek 12.0
END DESCRIPTION:
XS GIS Cut Line= 3
      1886574.97     13945524.98        1885875.       13945125.
        1884875.       13944125.
#Sta/Elev= 30
  4199.9  1748.5  4271.8 1743.45  4418.7 1729.73  4557.6  1725.9  4683.6 1725.45
  4727.5 1721.62  4799.5 1713.03  4842.9 1712.28    4955 1709.67  4956.6 1702.65
  4958.1 1701.65  5039.8 1702.65  5049.9 1704.18  5105.1 1705.52  5161.7 1713.94
  5223.1 1715.67  5366.8 1720.94  5374.4 1721.04  5571.8 1722.34  5804.2 1732.18
  5925.3 1741.02  5967.8 1745.34  5981.9 1749.68  6010.2  1750.1  6080.9 1771.03
  6145.7 1783.91  6165.7 1780.76  6267.9 1789.59  6363.7 1805.32  6420.3 1809.12
#Mann= 13 ,-1 , 0
  4199.9    .035       0  4271.8     .07       0  4727.5      .1       0
  4842.9     .07       0  4956.6     .05       0  5039.8     .07       0
  5049.9      .1       0  5223.1     .07       0  5366.8    .035       0
  5374.4     .05       0  5804.2     .07       0  6145.7      .1       0
  6267.9     .07       0
Bank Sta=4956.6,5039.8
XS Rating Curve= 0 ,0
Exp/Cntr=0.3,0.1

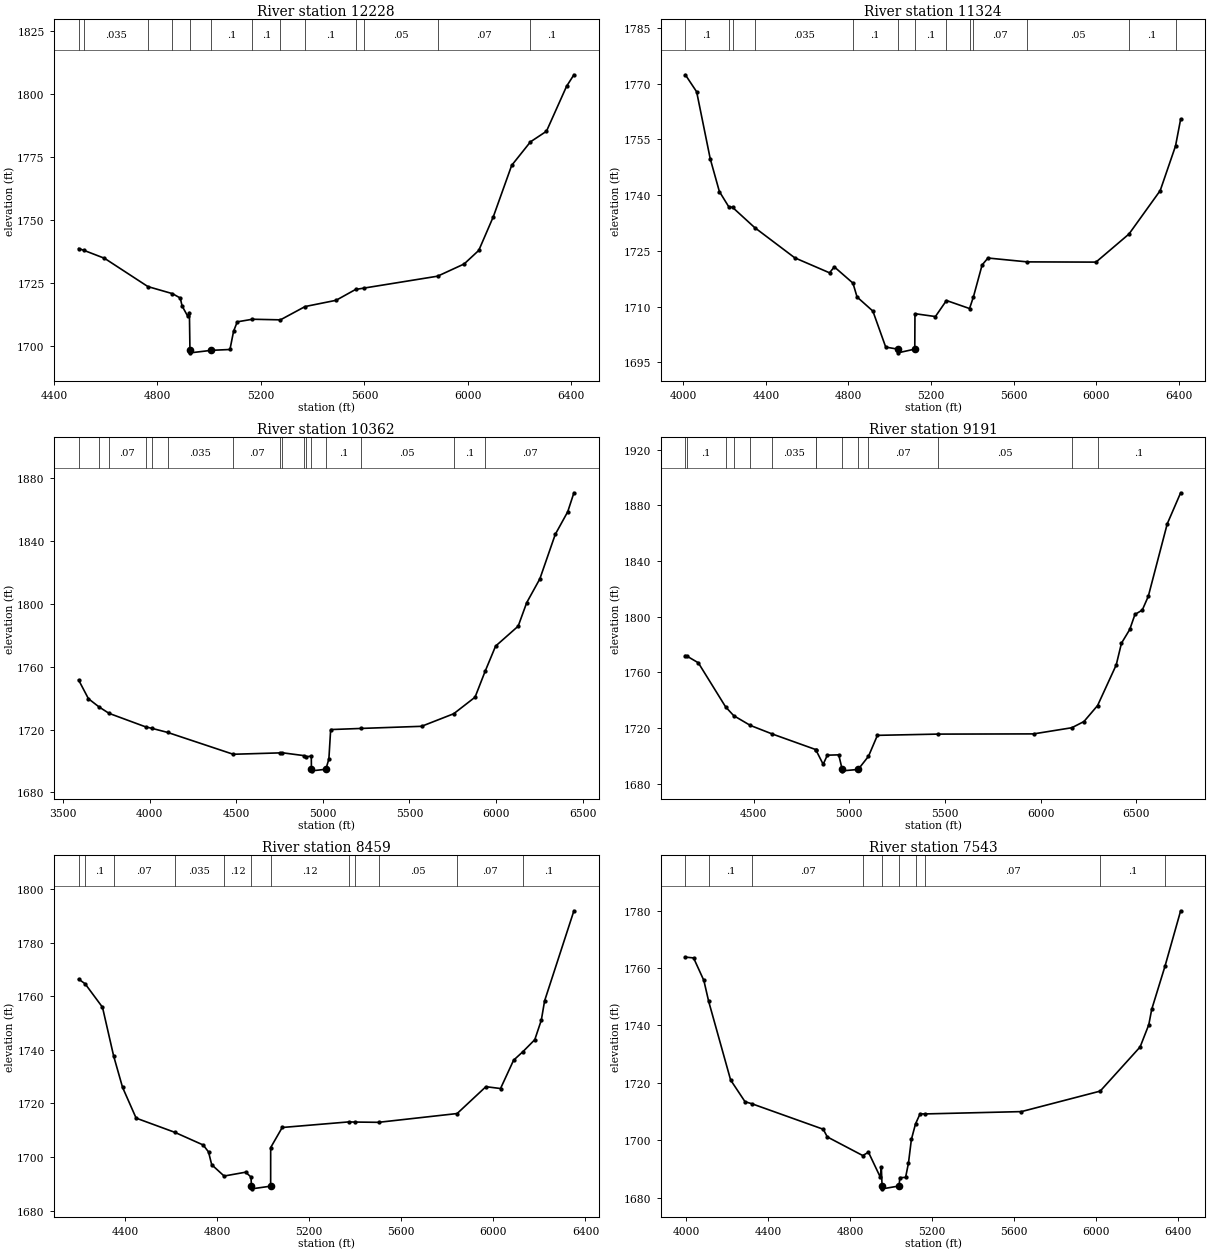
Type RM Length L Ch R = 1 ,12228   ,904,904,904
BEGIN DESCRIPTION:
Johnson Creek 11.0
END DESCRIPTION:
XS GIS Cut Line= 3
      1886825.04     13944825.03        1886425.       13944525.
      1885424.97     13943524.97
#Sta/Elev= 30
  4495.3  1738.6  4515.7 1737.88  4595.3 1734.72  4763.2 1723.46  4858.1 1720.65
  4888.1 1718.92  4895.3 1715.74  4917.2 1711.64  4923.5 1713.15  4925.6 1698.12
  4927.1 1697.12  5008.8 1698.12  5080.2 1698.45  5094.3 1705.74  5108.5 1709.45
  5167.2 1710.48  5275.3 1710.24  5370.7 1715.53  5490.3 1718.01  5565.7 1722.32
  5598.3 1722.87  5882.7  1727.6  5985.3 1732.46  6041.9 1737.86  6098.4 1751.33
  6169.1 1771.67  6241.6 1781.02  6303.5 1785.23  6381.3 1803.13  6409.6 1807.69
#Mann= 13 ,-1 , 0
  4495.3     .07       0  4515.7    .035       0  4763.2     .07       0
  4858.1      .1       0  4925.6     .05       0  5008.8      .1       0
  5167.2      .1       0  5275.3     .07       0  5370.7      .1       0
  5565.7     .07       0  5598.3     .05       0  5882.7     .07       0
  6241.6      .1       0
Bank Sta=4925.6,5008.8
XS Rating Curve= 0 ,0
Exp/Cntr=0.3,0.1

Type RM Length L Ch R = 1 ,11324   ,962,962,962
BEGIN DESCRIPTION:
Johnson Creek 10.0
END DESCRIPTION:
XS GIS Cut Line= 3
        1887725.       13944225.        1886825.       13943825.
        1885825.       13942825.
#Sta/Elev= 30
  4010.1  1772.4  4064.8 1767.82  4130.5 1749.81  4174.9 1740.96  4219.8 1736.91
  4239.2 1736.68  4345.6 1731.27  4540.2 1723.11  4708.4 1719.08  4731.7 1720.67
  4821.9  1716.3  4841.8 1712.57  4918.4 1708.77  4980.6 1699.08  5038.2 1698.53
  5039.7 1697.53  5121.4 1698.53  5122.3 1708.07  5221.3  1707.3  5274.8 1711.62
  5386.7 1709.46  5405.6 1712.63  5447.5 1721.19  5475.8 1723.06  5666.4 1722.02
  5999.1 1721.96  6158.9 1729.52  6310.2 1741.22  6384.3 1753.21  6409.2 1760.45
#Mann= 13 ,-1 , 0
  4010.1      .1       0  4219.8     .07       0  4239.2      .1       0
  4345.6    .035       0  4821.9      .1       0  5038.2     .05       0
  5121.4      .1       0  5274.8    .035       0  5386.7      .1       0
  5405.6     .07       0  5666.4     .05       0  6158.9      .1       0
  6384.3     .07       0
Bank Sta=5038.2,5121.4
XS Rating Curve= 0 ,0
Exp/Cntr=0.3,0.1

Type RM Length L Ch R = 1 ,10362   ,1171,1171,1171
BEGIN DESCRIPTION:
Johnson Creek 9.0
END DESCRIPTION:
XS GIS Cut Line= 3
      1887775.03     13943975.03        1886775.       13942975.
      1885370.25     13942633.13
#Sta/Elev= 30
    3590 1751.46  3646.6 1739.58  3708.7 1734.29    3766 1730.26  3977.2 1721.68
    4014 1720.73  4104.2 1718.15  4482.7 1704.28  4753.6 1705.16  4766.9 1705.22
  4888.7 1703.45  4904.2 1702.75  4933.5 1703.06  4934.3 1694.75  4935.8 1693.75
  5017.6 1694.75  5035.1 1701.31  5045.4 1719.97  5220.6 1720.69  5570.2 1722.04
  5755.8 1730.02  5879.1 1740.54  5937.3 1756.98  5997.7 1772.99  6128.1 1785.66
  6177.5 1800.63  6253.3 1815.72  6342.2 1843.96  6414.2 1858.34    6450 1870.41
#Mann= 16 ,-1 , 0
    3590     .07       0  3708.7      .1       0    3766     .07       0
  3977.2    .035       0    4014     .07       0  4104.2    .035       0
  4482.7     .07       0  4753.6      .1       0  4766.9      .1       0
  4888.7      .1       0  4904.2      .1       0  4934.3     .05       0
  5017.6      .1       0  5220.6     .05       0  5755.8      .1       0
  5937.3     .07       0
Bank Sta=4934.3,5017.6
XS Rating Curve= 0 ,0
Exp/Cntr=0.3,0.1

Type RM Length L Ch R = 1 ,9191    ,732,732,732
BEGIN DESCRIPTION:
Johnson Creek 8.0
END DESCRIPTION:
XS GIS Cut Line= 3
      1888174.99     13943574.99      1887756.02     13942813.72
      1887250.24     13941170.44
#Sta/Elev= 30
  4143.6 1772.11  4151.7 1771.76  4211.3 1766.95  4354.3  1735.2  4396.5 1728.94
  4483.4 1721.93  4597.7 1715.79  4824.1 1704.63  4826.2 1704.21  4863.8 1693.99
  4885.5 1700.55  4945.2  1700.8  4963.2  1690.3  4964.7  1689.3  5046.5  1690.3
  5100.6 1699.75  5147.2 1714.81  5462.4  1715.7  5963.3 1715.85  6163.2 1720.28
  6226.5 1724.73  6297.9 1736.24  6395.2 1765.41  6422.6 1781.04  6465.8 1790.88
  6493.2 1801.73  6531.2 1804.81  6562.8 1814.73  6661.9 1866.85  6731.9 1889.14
#Mann= 14 ,-1 , 0
  4143.6    .035       0  4151.7      .1       0  4354.3     .07       0
  4396.5      .1       0  4483.4     .07       0  4597.7    .035       0
  4824.1     .07       0  4826.2      .1       0  4963.2     .05       0
  5046.5      .1       0  5100.6     .07       0  5462.4     .05       0
  6163.2     .07       0  6297.9      .1       0
Bank Sta=4963.2,5046.5
XS Rating Curve= 0 ,0
Exp/Cntr=0.3,0.1

Type RM Length L Ch R = 1 ,8459    ,916,916,916
BEGIN DESCRIPTION:
Johnson Creek 7.0
END DESCRIPTION:
XS GIS Cut Line= 3
      1888725.01     13943125.02        1888325.       13942425.
        1887425.     13941425.01
#Sta/Elev= 30
  4198.1 1766.42  4226.3 1764.67  4301.8  1755.9  4350.3 1737.68  4388.9    1726
  4447.9  1714.5  4616.1 1709.19  4739.4 1704.46  4762.5 1701.86  4776.2  1697.1
  4830.2 1692.87  4923.7 1694.31  4946.8  1692.5    4949 1689.09  4950.5 1688.09
  5032.3 1689.09  5032.4  1703.5  5082.5    1711  5370.6 1713.08  5399.1 1713.03
  5500.9 1712.93  5842.4 1716.21  5967.4 1726.24  6030.9 1725.55  6087.7 1736.13
  6128.8 1739.37  6179.7 1743.79  6208.1 1751.09  6222.3 1758.27  6349.7 1791.93
#Mann= 12 ,-1 , 0
  4198.1    .035       0  4226.3      .1       0  4350.3     .07       0
  4616.1    .035       0  4830.2     .12       0    4949     .05       0
  5032.3     .12       0  5370.6     .05       0  5399.1     .07       0
  5500.9     .05       0  5842.4     .07       0  6128.8      .1       0
Bank Sta=4949,5032.3
XS Rating Curve= 0 ,0
Exp/Cntr=0.3,0.1

Type RM Length L Ch R = 1 ,7543    ,902,902,902
BEGIN DESCRIPTION:
Johnson Creek 6.0
END DESCRIPTION:
XS GIS Cut Line= 3
        1889025.     13943074.98        1889125.       13942075.
      1888124.99     13941074.99
#Sta/Elev= 30
  3995.7 1763.79  4035.9 1763.51  4086.1 1755.65  4109.6 1748.37  4216.8 1720.99
  4287.1 1713.43  4322.1 1712.68    4669 1703.84  4689.1 1701.16  4862.1 1694.68
  4890.1 1695.83  4947.9 1687.15  4952.9 1690.74  4956.5 1684.08    4958 1683.08
  5039.8 1684.08  5043.1 1686.98  5071.4 1687.06  5085.5 1692.07  5099.7 1700.29
    5120 1705.72  5142.1  1709.2  5165.7 1709.17  5637.1 1709.98  6021.9 1717.12
  6216.9  1732.5  6259.3 1740.25  6273.5 1745.59  6338.5 1760.64  6414.9 1779.93
#Mann= 10 ,-1 , 0
  3995.7    .035       0  4109.6      .1       0  4322.1     .07       0
  4862.1    .035       0  4956.5     .05       0  5039.8    .035       0
    5120    .035       0  5165.7     .07       0  6021.9      .1       0
  6338.5     .07       0
Bank Sta=4956.5,5039.8
XS Rating Curve= 0 ,0
Exp/Cntr=0.3,0.1

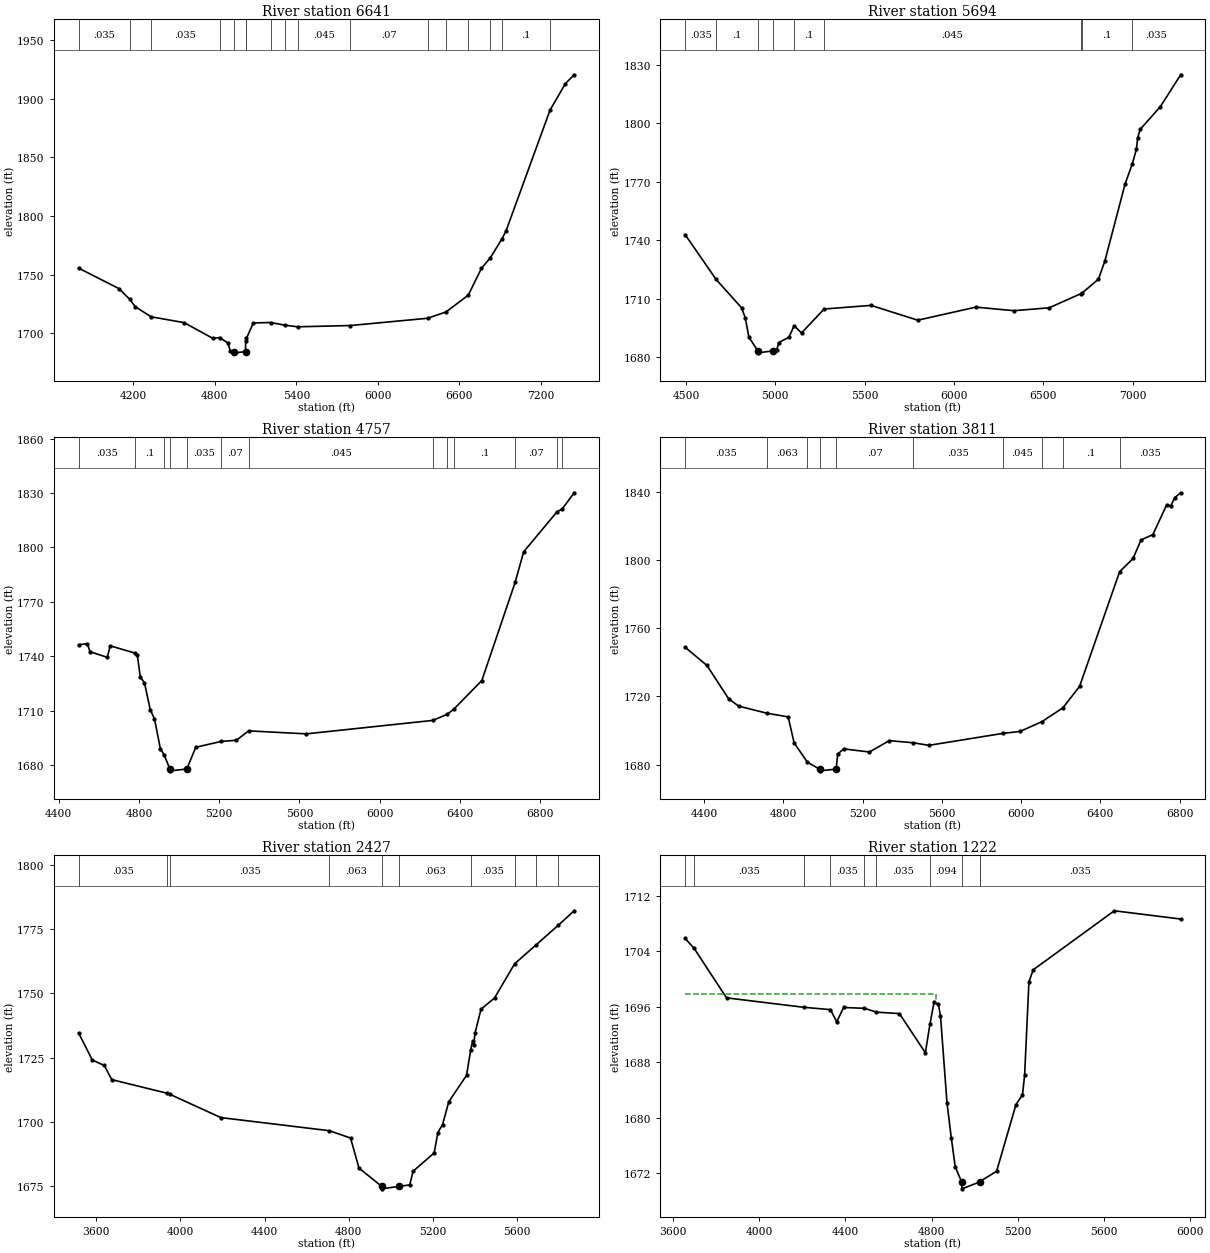
Type RM Length L Ch R = 1 ,6641    ,947,947,947
BEGIN DESCRIPTION:
Johnson Creek 5.0
END DESCRIPTION:
XS GIS Cut Line= 3
      1889898.85     13943082.36        1889875.       13941875.
      1887875.01       13940475.
#Sta/Elev= 30
  3796.9 1755.61  4094.3 1738.11  4173.3 1728.96  4214.3 1722.66  4331.6 1714.08
  4574.4  1709.1  4784.5 1695.74  4835.5  1696.4  4894.5  1691.9  4914.5 1684.95
  4942.8 1684.36  4944.3 1683.36  5026.1 1684.36  5026.7 1693.29  5032.2 1695.65
  5083.4 1708.85    5212 1709.24  5316.2 1706.94  5409.8 1705.57  5797.7 1706.65
  6366.4 1712.85  6502.4 1718.25  6665.8 1732.52  6762.7 1755.32  6829.4 1764.67
    6915  1780.7    6944 1787.38  7268.1 1890.42  7381.7 1913.11  7445.8 1920.55
#Mann= 17 ,-1 , 0
  3796.9    .035       0  4173.3     .07       0  4331.6    .035       0
  4835.5     .07       0  4942.8     .05       0  5026.1     .07       0
  5032.2      .1       0    5212    .045       0  5316.2     .07       0
  5409.8    .045       0  5797.7     .07       0  6366.4    .045       0
  6502.4     .07       0  6665.8      .1       0  6829.4     .07       0
    6915      .1       0  7268.1     .07       0
Bank Sta=4942.8,5026.1
XS Rating Curve= 0 ,0
Exp/Cntr=0.3,0.1

Type RM Length L Ch R = 1 ,5694    ,937,937,937
BEGIN DESCRIPTION:
Johnson Creek 4.0
END DESCRIPTION:
XS GIS Cut Line= 3
      1891024.97     13941275.01        1890525.       13941375.
      1888925.01     13939775.01
#Sta/Elev= 30
  4495.5 1742.95  4668.2 1720.05  4811.6 1705.43    4832 1700.35  4852.4 1690.44
  4902.4 1683.38  4903.9 1682.38    4986 1683.38  5008.9 1684.05  5019.5 1687.66
  5076.1 1690.33  5105.7 1696.29  5146.8 1692.55  5273.2 1704.82  5535.7 1706.68
  5797.3 1699.09  6122.6 1705.79  6334.7 1703.96  6532.7 1705.44    6710 1712.68
  6715.9 1712.92  6808.5 1720.14  6843.8 1729.28    6957 1768.76  6997.4 1779.11
  7020.6  1786.6  7027.7 1792.51  7041.8  1796.8    7155 1808.49  7268.1 1824.76
#Mann= 9 ,-1 , 0
  4495.5    .035       0  4668.2      .1       0  4902.4     .05       0
    4986      .1       0  5105.7      .1       0  5273.2    .045       0
    6710     .07       0  6715.9      .1       0  6997.4    .035       0
Bank Sta=4902.4,4986
XS Rating Curve= 0 ,0
Exp/Cntr=0.3,0.1

Type RM Length L Ch R = 1 ,4757    ,946,946,946
BEGIN DESCRIPTION:
Johnson Creek 3.0
END DESCRIPTION:
XS GIS Cut Line= 3
        1891175.       13940825.        1890775.       13940525.
      1888974.97     13939724.99
#Sta/Elev= 30
  4499.6 1746.31  4542.3 1746.87  4556.9 1742.45  4642.3 1739.34  4656.9  1745.7
  4778.8 1741.75  4792.3 1740.48  4806.9 1728.43  4827.7 1725.36  4856.9 1710.31
  4877.7 1705.42  4906.9    1689  4925.1 1685.67  4954.7 1677.74  4956.2 1676.74
  5038.3 1677.74  5083.7 1689.76  5209.2 1692.94  5286.2 1693.62  5346.7 1698.79
  5634.3 1697.14  6265.5 1704.57  6336.3 1707.92  6369.2 1710.72  6509.1 1726.53
  6675.1 1780.69  6717.7 1797.55  6883.2 1819.55  6909.6 1821.19  6969.4 1830.12
#Mann= 13 ,-1 , 0
  4499.6    .035       0  4778.8      .1       0  4925.1    .035       0
  4954.7     .05       0  5038.3    .035       0  5209.2     .07       0
  5346.7    .045       0  6265.5     .07       0  6336.3    .035       0
  6369.2      .1       0  6675.1     .07       0  6883.2    .035       0
  6909.6     .07       0
Bank Sta=4954.7,5038.3
XS Rating Curve= 0 ,0
Exp/Cntr=0.3,0.1

Type RM Length L Ch R = 1 ,3811    ,1384,1384,1384
BEGIN DESCRIPTION:
Johnson Creek 2.0
END DESCRIPTION:
XS GIS Cut Line= 3
      1891524.98       13939675.        1890825.       13939675.
      1889024.98       13939675.
#Sta/Elev= 30
  4304.8 1748.94  4414.8 1738.27  4524.8 1718.59  4574.8 1714.34  4717.3 1710.16
  4824.8 1707.99  4854.8 1692.72  4921.7 1681.41  4982.9 1677.29  4984.4 1676.29
  5066.7 1677.29  5074.8 1686.14  5104.8  1689.2  5234.8 1687.36  5334.8 1694.04
    5457 1692.77  5534.8 1691.28  5907.7  1698.3  5994.8 1699.45  6104.8 1705.19
  6210.5 1713.31  6294.8 1725.88  6497.1 1793.37  6564.8 1801.11  6604.8    1812
  6664.8 1815.16  6734.8 1832.79  6754.8 1831.91  6774.8 1836.83  6804.8 1839.74
#Mann= 10 ,-1 , 0
  4304.8    .035       0  4717.3    .063       0  4921.7     .07       0
  4982.9     .05       0  5066.7     .07       0    5457    .035       0
  5907.7    .045       0  6104.8     .07       0  6210.5      .1       0
  6497.1    .035       0
Bank Sta=4982.9,5066.7
XS Rating Curve= 0 ,0
Exp/Cntr=0.3,0.1

Type RM Length L Ch R = 1 ,2427    ,1205,1205,1205
BEGIN DESCRIPTION:
Johnson Creek 1.1
END DESCRIPTION:
XS GIS Cut Line= 4
      1891441.82     13939468.25      1890688.44      13938944.3
      1890002.12     13938878.45      1889279.88     13939075.96
#Sta/Elev= 30
  3516.2 1734.61  3581.3 1724.09    3638 1721.99  3673.8 1716.47  3935.2 1711.21
  3948.9  1710.8  4192.3  1701.7  4708.6 1696.59    4809 1693.73  4849.2 1682.03
  4956.6 1674.97  4958.1 1673.97  5040.6 1674.97  5090.3 1675.48  5106.2 1680.81
  5206.8 1687.98    5224 1695.88  5246.4 1698.98  5275.8 1707.83  5360.3 1718.13
  5380.1 1728.04  5389.7 1731.58  5394.8 1730.11  5400.3 1734.47  5429.3 1743.89
  5493.6 1748.26  5589.2 1761.59  5692.3    1769  5795.4 1776.49  5872.1 1782.19
#Mann= 10 ,-1 , 0
  3516.2    .035       0  3935.2    .063       0  3948.9    .035       0
  4708.6    .063       0  4956.6     .05       0  5040.6    .063       0
  5380.1    .035       0  5589.2      .1       0  5692.3    .035       0
  5795.4      .1       0
Bank Sta=4956.6,5040.6
XS Rating Curve= 0 ,0
Exp/Cntr=0.3,0.1

Type RM Length L Ch R = 1 ,1222    ,130,130,130
BEGIN DESCRIPTION:
Johnson Creek 1.2
END DESCRIPTION:
XS GIS Cut Line= 4
      1891716.66     13938020.59      1890463.22     13937933.79
      1890063.91     13937937.26      1889421.53     13937923.37
#Sta/Elev= 30
  3656.7 1705.84  3698.7  1704.4  3848.8 1697.27  4206.5 1695.91  4330.6 1695.57
    4360 1693.81    4392 1695.88  4488.6 1695.76  4543.7 1695.21  4650.7    1695
    4771 1689.35  4792.6 1693.52  4811.1 1696.62  4831.2 1696.37  4841.2 1694.68
  4871.3 1682.16  4891.3 1677.06  4909.7 1672.86  4939.4 1670.72  4940.9 1669.72
  5023.4 1670.72  5025.5 1670.81  5101.4 1672.25  5191.4 1681.88  5221.4 1683.27
  5231.4  1686.1  5251.4 1699.58  5271.4 1701.32  5647.4 1709.83    5955 1708.64
#Mann= 10 ,-1 , 0
  3656.7    .094       0  3698.7    .035       0  4206.5    .063       0
  4330.6    .035       0  4488.6    .063       0  4543.7    .035       0
  4792.6    .094       0  4939.4     .05       0  5023.4    .094       0
  5025.5    .035       0
#XS Ineff= 2 , 0
         4821.06 1697.82
Permanent Ineff=
       F       F
Bank Sta=4939.4,5023.4
XS Rating Curve= 0 ,0
Exp/Cntr=0.3,0.1