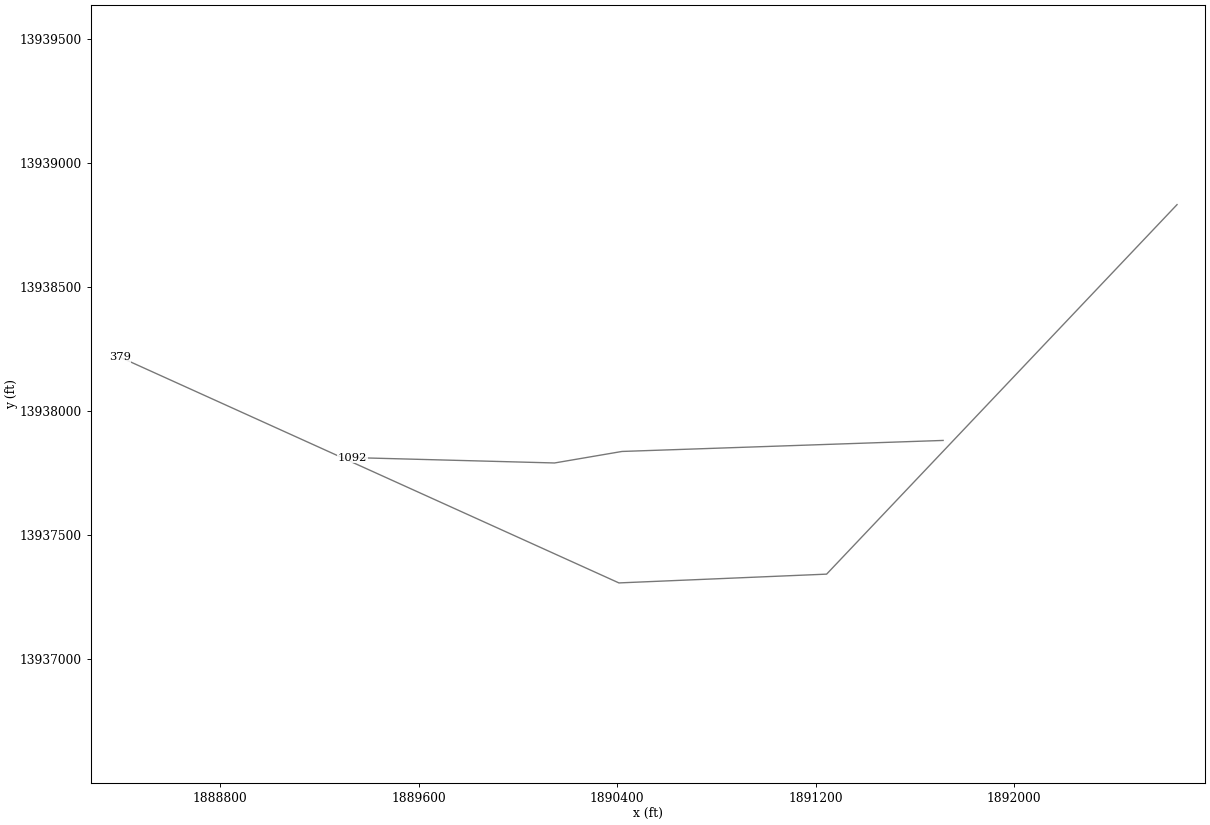
HEC-RAS study Johnson Creek.prj: Johnson Creek Base Level Engineering

--- Johnson Creek.g01 (geometry) --- (continued)

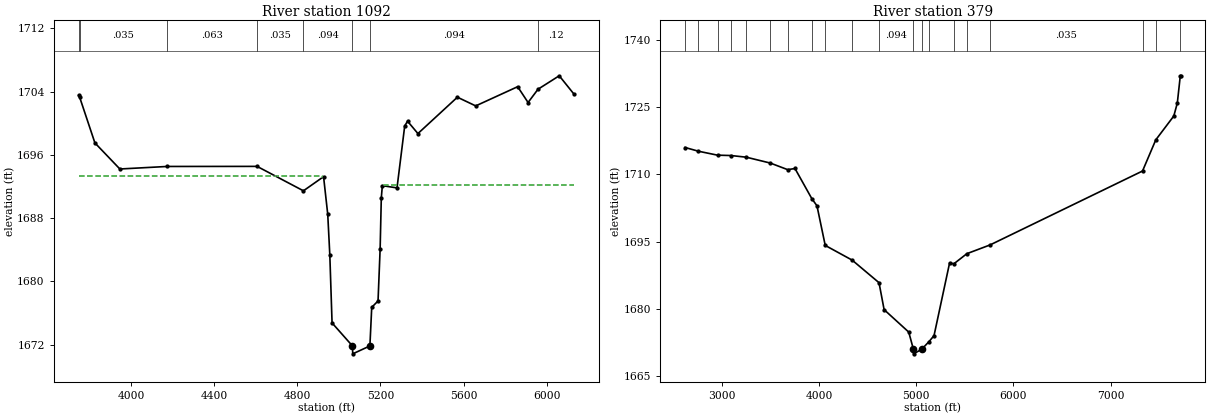
Type RM Length L Ch R = 1 ,1092    ,713,713,713
BEGIN DESCRIPTION:
Johnson Creek 1.0
END DESCRIPTION:
XS GIS Cut Line= 4
      1891713.25      13937881.7      1890418.83     13937837.27
      1890146.95     13937790.85      1889333.14     13937812.55
#Sta/Elev= 30
  3747.2 1703.53  3752.5 1703.27  3825.5 1697.52  3945.6 1694.22  4173.5 1694.54
  4606.1 1694.55  4829.2 1691.46  4926.1 1693.25  4946.2 1688.48  4956.2 1683.34
    4967 1674.75  5065.1 1671.84  5066.6 1670.84  5149.1 1671.84  5157.9 1676.72
  5188.3 1677.53  5198.4 1684.14    5204 1690.56    5209 1692.11  5279.6 1691.83
  5316.6 1699.65  5330.2 1700.27  5380.2  1698.7  5570.2  1703.3  5658.4  1702.2
  5860.3 1704.63  5910.4 1702.63  5958.3 1704.31  6060.4 1706.01  6132.3 1703.66
#Mann= 8 ,-1 , 0
  3747.2    .063       0  3752.5    .035       0  4173.5    .063       0
  4606.1    .035       0  4829.2    .094       0  5065.1     .05       0
  5149.1    .094       0  5958.3     .12       0
#XS Ineff= 2 , 0
          4918.6 1693.31 5217.05         1692.21
Permanent Ineff=
       F       F
Bank Sta=5065.1,5149.1
XS Rating Curve= 0 ,0
Exp/Cntr=0.3,0.1

Type RM Length L Ch R = 1 ,379     ,0,0,0
BEGIN DESCRIPTION:
Johnson Creek 0.0
END DESCRIPTION:
XS GIS Cut Line= 4
      1892656.25     13938832.27      1891243.61     13937342.72
      1890406.29     13937307.32       1888393.8       13938218.
#Sta/Elev= 30
  2620.4    1716  2757.8 1715.17    2954 1714.29  3092.6 1714.21  3250.1 1713.84
  3497.6 1712.53  3676.4 1711.06  3751.1 1711.32    3924 1704.62  3977.6    1703
  4062.6 1694.17  4339.8 1690.89  4616.2 1685.86  4668.6 1679.85  4922.1 1674.85
  4970.2    1671  4971.7    1670  5054.2    1671  5130.1 1672.71  5182.3 1674.06
  5342.5 1690.27  5386.2 1690.07  5520.4 1692.33  5759.2 1694.28  7328.1 1710.76
  7464.4  1717.7    7650 1723.02  7686.1 1725.91  7716.6 1731.95  7720.3 1731.99
#Mann= 20 ,-1 , 0
  2620.4    .035       0  2757.8    .063       0    2954    .063       0
  3092.6    .063       0  3250.1     .12       0  3497.6    .035       0
  3676.4    .094       0    3924    .035       0  4062.6    .035       0
  4339.8    .094       0  4616.2    .094       0  4970.2     .05       0
  5054.2    .094       0  5130.1      .1       0  5386.2    .035       0
  5520.4    .094       0  5759.2    .035       0  7328.1    .094       0
  7464.4    .094       0  7716.6    .063       0
Bank Sta=4970.2,5054.2
XS Rating Curve= 0 ,0
Exp/Cntr=0.3,0.1

Chan Stop Cuts=-1
Use User Specified Reach Order=0
Composite Channel Slope=5