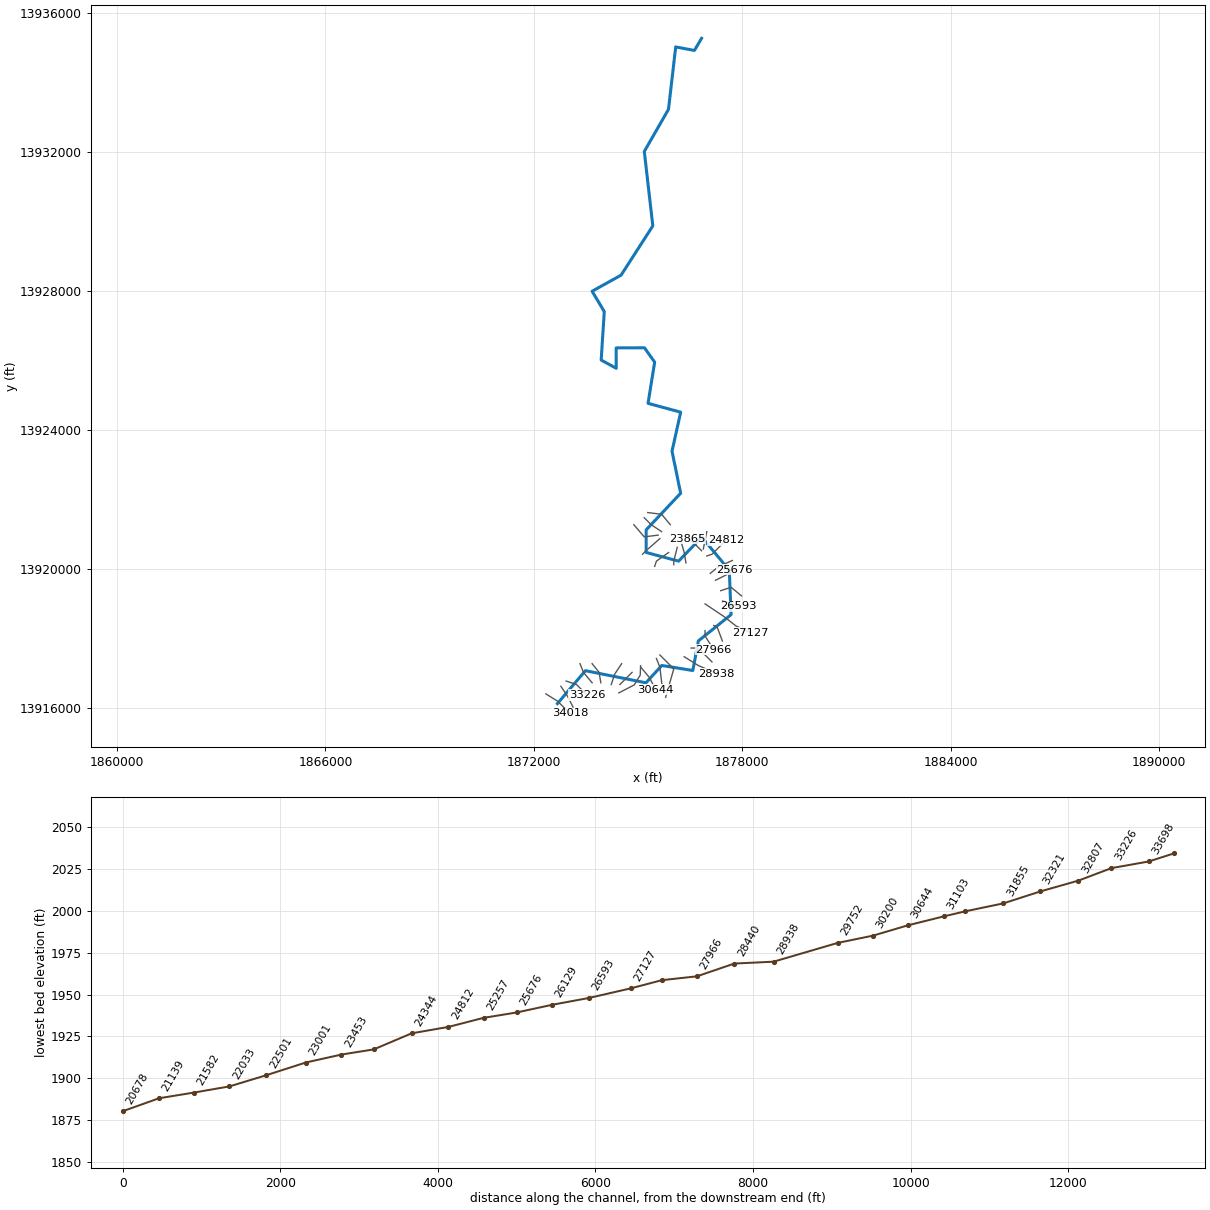
--- Kelley Creek.prj (project) ---

Proj Title=Kelley Creek Base Level Engineering
Current Plan=p01
Default Exp/Contr=0.3,0.1
English Units
Geom File=g01
Flow File=f01
Plan File=p01
BEGIN DESCRIPTION:
Kelley Creek
END DESCRIPTION:

--- Kelley Creek.p01 (plan) ---

Plan Title=Multiple Run
Short Identifier=Multiple
Geom File=g01
Flow File=f01
Subcritical Flow
K Sum by GR= 0
Std Step Tol= 0.01
Critical Tol= 0.01
Num of Std Step Trials= 20
Max Error Tol= 0.3
Flow Tol Ratio= 0.001
Split Flow NTrial= 30
Split Flow Tol= 0.02
Split Flow Ratio= 0.02
Log Output Level= 0
Friction Slope Method= 1
Unsteady Friction Slope Method= 2
Unsteady Bridges Friction Slope Method= 1
Parabolic Critical Depth
Global Vel Dist=  1 , 1 , 1
Global Log Level= 0
CheckData=True
Encroach Param= -1, 0, 0, 0
BEGIN DESCRIPTION:
Multiple Run
END DESCRIPTION:

--- Kelley Creek.f01 (steady flow) ---

Flow Title=Multiple
Number of Profiles=7
Profile Names=10-year,25-year,50-year,1pct_min,100-year,1pct_plu,500-year
River Rch & RM= Kelley Creek,Reach-1,34018
    1036    1763    2454    1652    3296    6576    5871
River Rch & RM= Kelley Creek,Reach-1,30644
    1773    3107    4410    3020    6026   12023   11122
River Rch & RM= Kelley Creek,Reach-1,26593
    2351    4175    5976    4122    8224   16410   15409
River Rch & RM= Kelley Creek,Reach-1,21582
    2980    5348    7707    5348   10672   21293   20242
River Rch & RM= Kelley Creek,Reach-1,17006
    3240    5824    8403    5836   11644   23233   22119
River Rch & RM= Kelley Creek,Reach-1,11575
    3717    6720    9733    6782   13532   27000   25881
River Rch & RM= Kelley Creek,Reach-1,9281
    4148    7527   10930    7632   15229   30385   29252
River Rch & RM= Kelley Creek,Reach-1,3725
    4641    8460   12321    8627   17213   34344   33242
Boundary for River Rch & Prof#=Kelley Creek,Reach-1,1
Up Type=0
Dn Type=3
Dn Slope=0.005
Boundary for River Rch & Prof#=Kelley Creek,Reach-1,2
Up Type=0
Dn Type=3
Dn Slope=0.005
Boundary for River Rch & Prof#=Kelley Creek,Reach-1,3
Up Type=0
Dn Type=3
Dn Slope=0.005
Boundary for River Rch & Prof#=Kelley Creek,Reach-1,4
Up Type=0
Dn Type=3
Dn Slope=0.005
Boundary for River Rch & Prof#=Kelley Creek,Reach-1,5
Up Type=0
Dn Type=3
Dn Slope=0.005
Boundary for River Rch & Prof#=Kelley Creek,Reach-1,6
Up Type=0
Dn Type=3
Dn Slope=0.005
Boundary for River Rch & Prof#=Kelley Creek,Reach-1,7
Up Type=0
Dn Type=3
Dn Slope=0.005

--- Kelley Creek.g01 (geometry) ---

Geom Title=Existing Conditions

River Reach=Kelley Creek,Reach-1
Reach XY= 30
      1872675.00     13916125.00      1873480.67     13917073.02
      1875225.00     13916725.00      1875680.45     13917222.83
      1876573.65     13917078.27      1876732.80     13917931.21
      1877674.38     13918685.67      1877623.38     13919963.42
      1876831.19     13920917.19      1876163.17     13920226.62
      1875228.76     13920476.56      1875230.73     13921127.55
      1876222.76     13922180.93      1875974.56     13923390.18
      1876223.95     13924514.57      1875283.97     13924768.35
      1875475.10     13925954.90      1875181.19     13926367.18
      1874365.29     13926364.25      1874369.37     13925776.97
      1873935.11     13926015.05      1874024.62     13927409.84
      1873674.64     13927995.42      1874508.57     13928458.24
      1875421.57     13929876.22      1875176.80     13932018.89
      1875872.77     13933230.93      1876080.42     13935027.68
      1876619.11     13934926.96      1876825.00     13935275.00

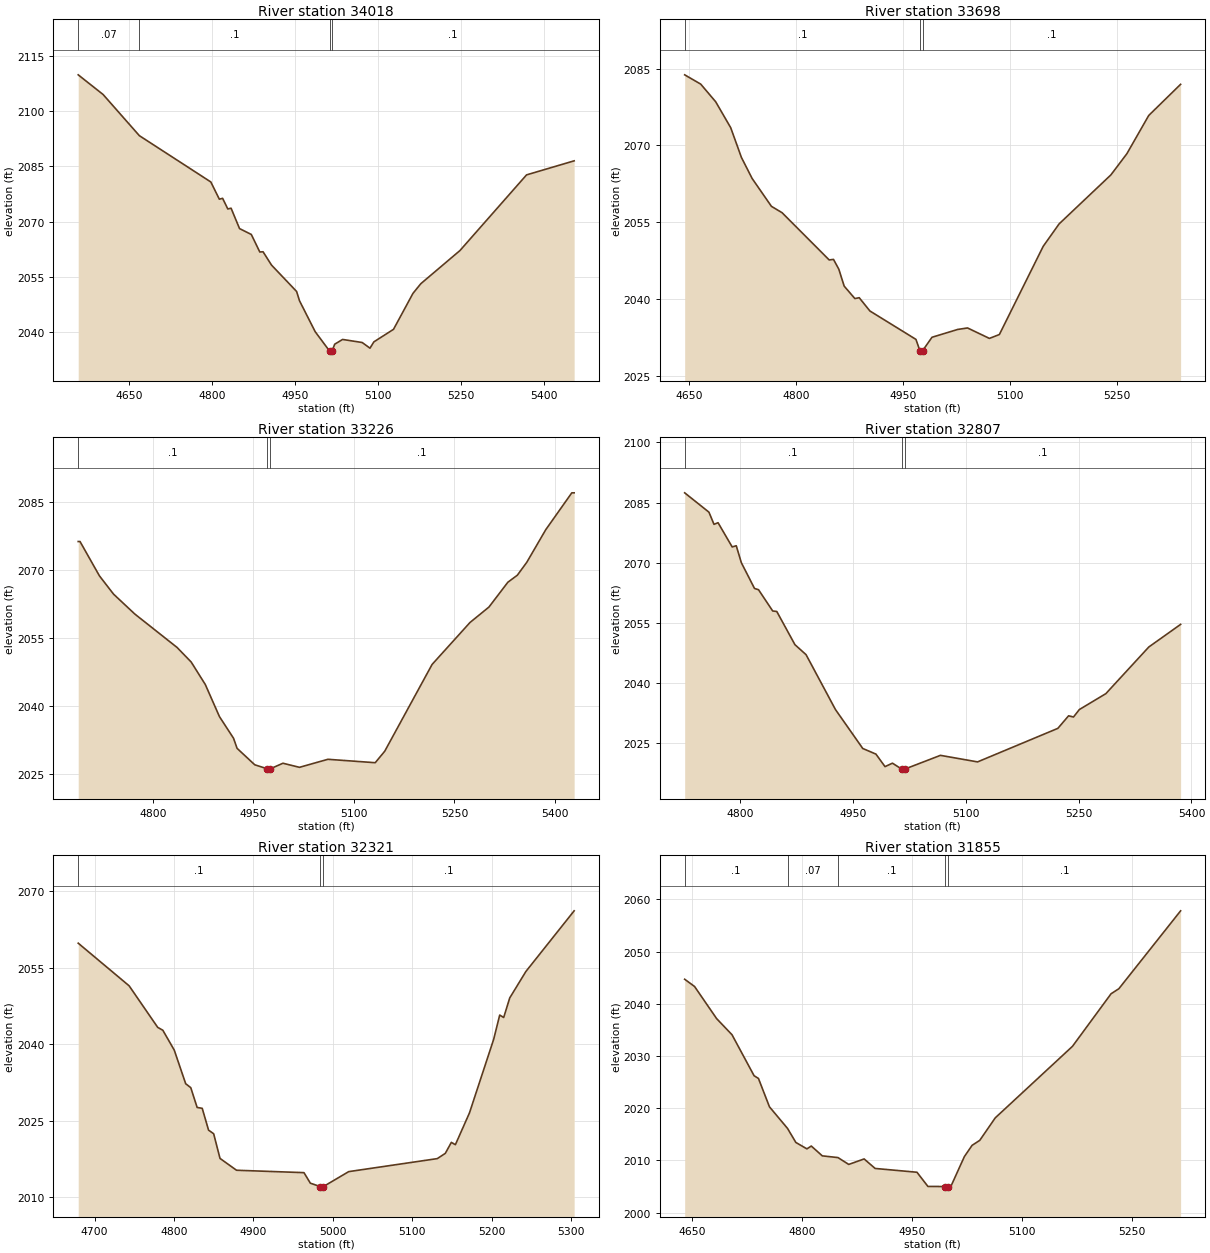
Type RM Length L Ch R = 1,34018,320,320,320
BEGIN DESCRIPTION:
Kelley Creek 68.0
END DESCRIPTION:
XS GIS Cut Line= 3
      1872343.83     13916405.11      1872676.51     13916197.41
      1873035.91     13915844.21
#Sta/Elev= 30
  4557.7 2109.79  4602.7 2104.45  4668.2 2093.29  4797.3 2080.74  4812.7 2076.07
  4818.6 2076.31  4828.0 2073.42  4833.9 2073.63  4849.2 2068.10  4870.5 2066.50
  4885.8 2061.75  4891.7 2061.81  4907.0 2058.20  4952.3 2051.05  4957.6 2048.51
  4985.9 2040.14  5012.2 2034.83  5012.5 2034.33  5016.2 2034.83  5021.2 2036.76
  5035.4 2038.04  5070.8 2037.21  5084.9 2035.67  5091.9 2037.38  5127.4 2040.78
  5162.6 2050.54  5176.8 2053.16  5247.5 2062.15  5367.8 2082.66  5453.8 2086.47
#Mann=4,-1,0
  4557.7    0.07       0  4668.2     0.1       0  5012.2    0.05       0
  5016.2     0.1       0
Bank Sta=5012.2,5016.2
Exp/Cntr=0.3,0.1

Type RM Length L Ch R = 1,33698,472,472,472
BEGIN DESCRIPTION:
Kelley Creek 67.0
END DESCRIPTION:
XS GIS Cut Line= 3
      1872775.01     13916624.98      1872975.00     13916325.00
      1873124.98     13916025.04
#Sta/Elev= 30
  4643.9 2083.77  4666.4 2081.96  4687.4 2078.52  4708.5 2073.46  4723.5 2067.67
  4738.5 2063.57  4765.6 2058.13  4780.6 2056.88  4846.7 2047.67  4852.7 2047.78
  4860.2 2045.87  4867.7 2042.57  4882.7 2040.14  4888.8 2040.31  4903.8 2037.72
  4968.4 2032.18  4973.9 2030.00  4974.1 2029.50  4977.9 2030.00  4990.9 2032.59
  5026.8 2034.11  5040.8 2034.41  5071.5 2032.37  5085.5 2033.13  5147.0 2050.33
  5169.3 2054.70  5242.0 2064.26  5264.4 2068.39  5295.1 2075.85  5339.8 2081.92
#Mann=3,-1,0
  4643.9     0.1       0  4973.9    0.05       0  4977.9     0.1       0
Bank Sta=4973.9,4977.9
Exp/Cntr=0.3,0.1

Type RM Length L Ch R = 1,33226,419,419,419
BEGIN DESCRIPTION:
Kelley Creek 66.0
END DESCRIPTION:
XS GIS Cut Line= 3
      1872924.96     13916775.01      1873225.00     13916675.00
      1873524.98     13916375.02
#Sta/Elev= 30
  4688.3 2076.23  4691.0 2076.23  4720.0 2068.65  4741.0 2064.63  4772.7 2060.24
  4835.9 2052.85  4857.0 2049.63  4878.1 2044.66  4899.2 2037.58  4920.2 2032.81
  4925.5 2030.58  4951.9 2026.95  4970.9 2026.05  4971.2 2025.55  4974.7 2025.55
  4974.9 2026.05  4994.0 2027.29  5018.7 2026.39  5061.1 2028.16  5131.8 2027.41
  5146.0 2029.95  5216.7 2049.10  5273.3 2058.36  5301.6 2061.77  5329.8 2067.24
  5344.0 2068.80  5358.1 2071.65  5386.4 2078.84  5425.3 2086.98  5428.8 2086.98
#Mann=3,-1,0
  4688.3     0.1       0  4970.9    0.05       0  4974.9     0.1       0
Bank Sta=4970.9,4974.9
Exp/Cntr=0.3,0.1

Type RM Length L Ch R = 1,32807,486,486,486
BEGIN DESCRIPTION:
Kelley Creek 65
END DESCRIPTION:
XS GIS Cut Line= 3
      1873325.01     13917274.97      1873425.00     13917025.00
      1873674.98     13916725.03
#Sta/Elev= 30
  4725.9 2087.41  4758.2 2082.59  4764.9 2079.56  4770.3 2079.97  4789.1 2073.93
  4794.5 2074.23  4801.3 2070.00  4818.8 2063.59  4824.1 2063.28  4843.0 2057.98
  4848.4 2057.86  4872.6 2049.58  4887.4 2047.09  4926.5 2033.42  4962.8 2023.73
  4980.3 2022.33  4992.4 2019.21  5002.3 2020.07  5014.6 2018.59  5014.9 2018.09
  5018.6 2018.59  5066.1 2022.02  5115.5 2020.39  5222.3 2028.74  5236.6 2031.87
  5243.1 2031.57  5250.9 2033.43  5286.1 2037.38  5343.3 2049.01  5385.6 2054.64
#Mann=3,-1,0
  4725.9     0.1       0  5014.6    0.05       0  5018.6     0.1       0
Bank Sta=5014.6,5018.6
Exp/Cntr=0.3,0.1

Type RM Length L Ch R = 1,32321,466,466,466
BEGIN DESCRIPTION:
Kelley Creek 64.0
END DESCRIPTION:
XS GIS Cut Line= 3
      1873674.98     13917275.03      1873875.00     13917025.00
      1873924.99     13916725.03
#Sta/Elev= 30
  4679.4 2059.80  4743.5 2051.44  4779.5 2043.29  4785.9 2042.74  4800.3 2038.84
  4814.7 2032.25  4821.1 2031.48  4829.1 2027.60  4835.5 2027.43  4843.5 2023.15
  4849.9 2022.45  4857.9 2017.61  4878.7 2015.29  4963.6 2014.82  4971.6 2012.76
  4984.0 2012.09  4984.2 2011.59  4988.0 2012.09  5019.9 2015.02  5131.4 2017.57
  5141.5 2018.60  5149.1 2020.75  5154.2 2020.30  5171.9 2026.52  5202.4 2040.96
  5210.0 2045.71  5215.0 2045.23  5222.6 2049.06  5242.9 2054.24  5303.7 2066.14
#Mann=3,-1,0
  4679.4     0.1       0  4984.0    0.05       0  4988.0     0.1       0
Bank Sta=4984,4988
Exp/Cntr=0.3,0.1

Type RM Length L Ch R = 1,31855,485,485,485
BEGIN DESCRIPTION:
Kelley Creek 63.0
END DESCRIPTION:
XS GIS Cut Line= 3
      1874525.01     13917275.01      1874325.00     13916975.00
      1874225.00     13916675.00
#Sta/Elev= 30
  4639.4 2044.69  4652.9 2043.30  4683.0 2037.15  4704.0 2034.06  4734.1 2026.22
  4740.1 2025.69  4755.1 2020.26  4779.8 2016.12  4791.1 2013.44  4806.2 2012.21
  4812.2 2012.75  4827.2 2010.87  4848.6 2010.54  4863.3 2009.23  4884.3 2010.28
  4899.3 2008.46  4956.4 2007.73  4971.4 2005.01  4995.0 2005.00  4995.2 2004.50
  4999.0 2005.00  5002.6 2005.00  5021.1 2010.73  5031.6 2012.88  5042.1 2013.84
  5063.2 2018.14  5168.6 2031.84  5221.3 2041.91  5231.9 2042.87  5316.2 2057.79
#Mann=5,-1,0
  4639.4     0.1       0  4779.8    0.07       0  4848.6     0.1       0
  4995.0    0.05       0  4999.0     0.1       0
Bank Sta=4995,4999
Exp/Cntr=0.3,0.1

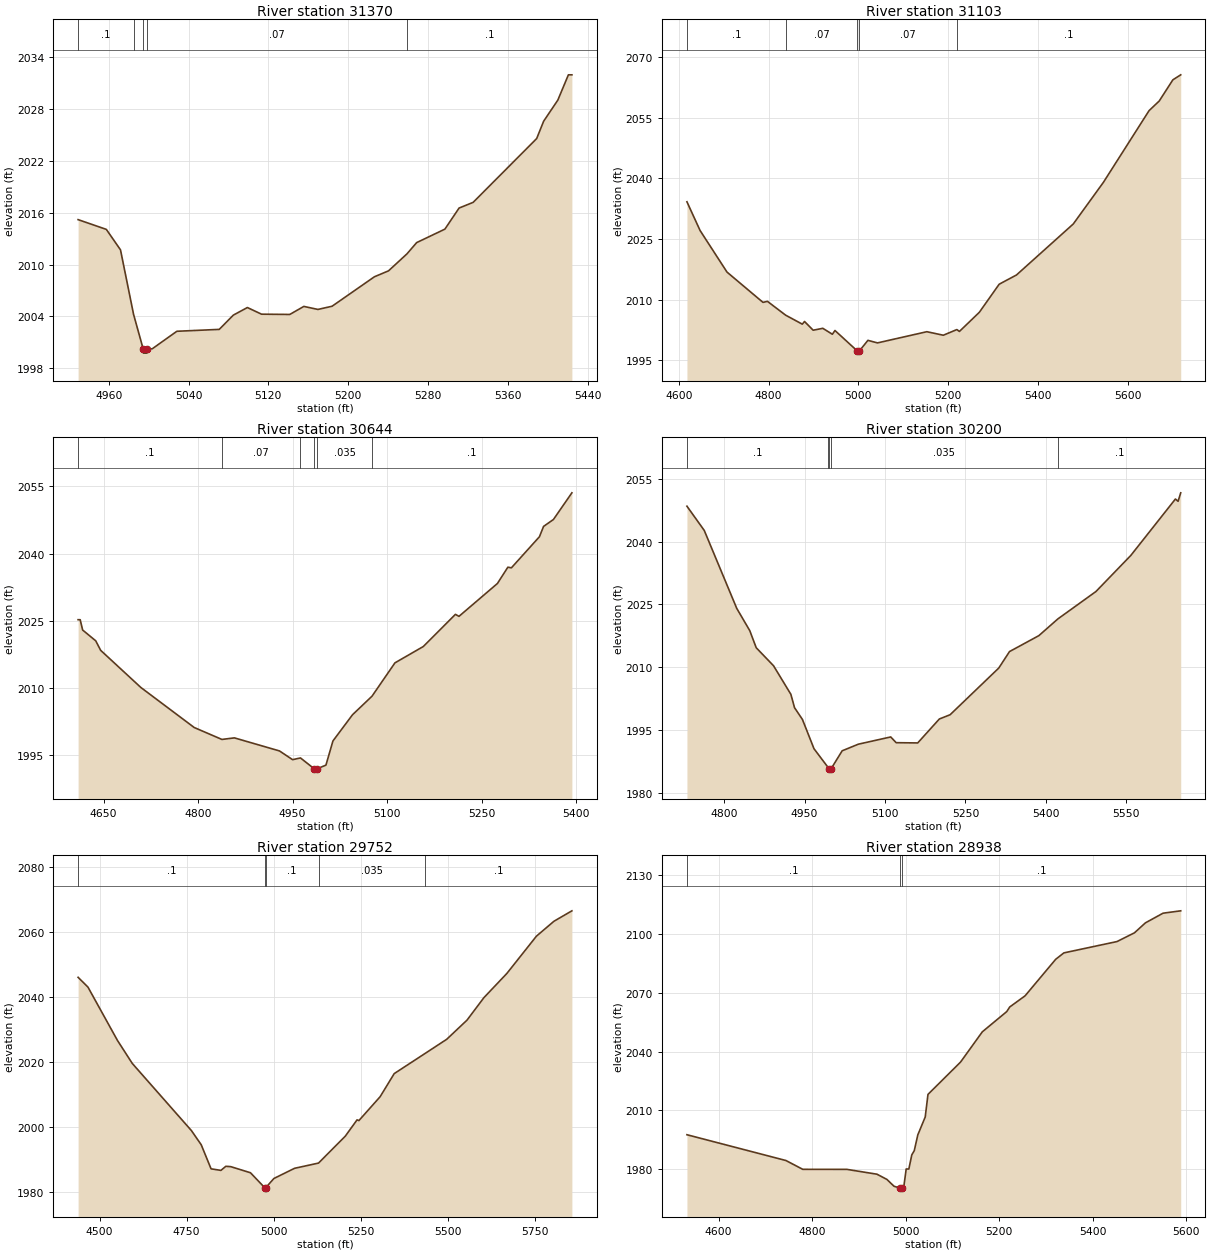
Type RM Length L Ch R = 1,31370,267,267,267
BEGIN DESCRIPTION:
Kelley Creek 62.0
END DESCRIPTION:
XS GIS Cut Line= 3
      1874825.02     13917025.02      1874775.00     13916975.00
      1874475.01     13916675.01
#Sta/Elev= 30
  4929.3 2015.20  4957.6 2014.07  4971.8 2011.70  4984.9 2004.23  4994.5 2000.24
  4994.8 1999.74  4998.3 1999.74  4998.5 2000.24  5003.6 2000.24  5028.3 2002.27
  5070.8 2002.49  5084.9 2004.14  5099.0 2005.02  5113.2 2004.25  5141.5 2004.22
  5155.6 2005.15  5169.7 2004.80  5183.9 2005.17  5226.3 2008.58  5240.5 2009.27
  5259.0 2011.24  5268.7 2012.54  5297.0 2014.10  5311.2 2016.54  5325.3 2017.20
  5389.0 2024.59  5396.0 2026.60  5410.2 2029.04  5420.8 2031.97  5424.3 2031.97
#Mann=5,-1,0
  4929.3     0.1       0  4984.9    0.07       0  4994.5    0.05       0
  4998.5    0.07       0  5259.0     0.1       0
Bank Sta=4994.5,4998.5
Exp/Cntr=0.3,0.1

Type RM Length L Ch R = 1,31103,459,459,459
BEGIN DESCRIPTION:
Kelley Creek 61.0
END DESCRIPTION:
XS GIS Cut Line= 4
      1875069.15     13917214.25      1875059.67     13916945.42
      1874885.54     13916662.80      1874442.43     13916433.01
#Sta/Elev= 30
  4618.2 2034.23  4647.5 2027.12  4707.5 2016.83  4787.6 2009.34  4797.6 2009.59
  4838.0 2006.18  4875.2 2003.95  4880.2 2004.61  4899.4 2002.45  4920.9 2002.92
  4942.2 2001.45  4948.0 2002.38  4998.1 1997.28  4998.4 1996.78  5002.1 1997.28
  5021.4 1999.94  5042.7 1999.31  5152.7 2002.08  5189.4 2001.21  5219.6 2002.61
  5225.3 2002.15  5269.6 2006.88  5313.8 2013.83  5352.4 2016.12  5478.9 2028.74
  5545.9 2039.02  5647.8 2056.79  5670.4 2059.17  5700.8 2064.41  5718.3 2065.65
#Mann=5,-1,0
  4618.2     0.1       0  4838.0    0.07       0  4998.1    0.05       0
  5002.1    0.07       0  5219.6     0.1       0
Bank Sta=4998.1,5002.1
Exp/Cntr=0.3,0.1

Type RM Length L Ch R = 1,30644,444,444,444
BEGIN DESCRIPTION:
Kelley Creek 73.0
END DESCRIPTION:
XS GIS Cut Line= 3
      1875074.99     13917175.01      1875325.00     13916875.00
      1875503.93     13916525.01
#Sta/Elev= 30
  4609.7 2025.23  4613.0 2025.23  4616.9 2022.93  4637.7 2020.51  4645.5 2018.39
  4709.3 2010.09  4793.9 2001.15  4837.9 1998.48  4857.7 1998.83  4929.3 1995.91
  4950.1 1993.96  4962.6 1994.35  4984.6 1991.90  4984.8 1991.40  4988.6 1991.90
  5003.0 1992.74  5014.1 1998.14  5045.2 2004.00  5076.1 2008.14  5112.5 2015.59
  5157.5 2019.24  5208.5 2026.43  5214.1 2025.98  5275.1 2033.32  5291.7 2036.96
  5297.3 2036.82  5341.8 2043.77  5348.4 2046.08  5364.0 2047.62  5393.3 2053.58
#Mann=6,-1,0
  4609.7     0.1       0  4837.9    0.07       0  4962.6   0.035       0
  4984.6   0.035       0  4988.6   0.035       0  5076.1     0.1       0
Bank Sta=4984.6,4988.6
Exp/Cntr=0.3,0.1

Type RM Length L Ch R = 1,30200,448,448,448
BEGIN DESCRIPTION:
Kelley Creek 72.0
END DESCRIPTION:
XS GIS Cut Line= 3
      1875525.01     13917424.98      1875625.00     13917175.00
      1875700.91     13916527.97
#Sta/Elev= 30
  4730.8 2048.46  4763.1 2042.67  4823.7 2024.06  4847.9 2018.77  4860.0 2014.67
  4892.3 2010.37  4924.6 2003.55  4931.4 2000.37  4946.2 1997.54  4967.7 1990.57
  4994.0 1986.10  4995.3 1985.72  4995.6 1985.22  4999.3 1985.72  5020.2 1990.07
  5050.4 1991.65  5110.8 1993.38  5120.9 1992.01  5161.1 1991.95  5201.4 1997.66
  5221.5 1998.68  5312.2 2009.82  5332.3 2013.76  5387.0 2017.56  5422.3 2021.54
  5493.4 2028.09  5558.4 2036.70  5641.6 2050.17  5646.6 2049.63  5651.5 2051.65
#Mann=5,-1,0
  4730.8     0.1       0  4994.0   0.035       0  4995.3   0.035       0
  4999.3   0.035       0  5422.3     0.1       0
Bank Sta=4995.3,4999.3
Exp/Cntr=0.3,0.1

Type RM Length L Ch R = 1,29752,814,814,814
BEGIN DESCRIPTION:
Kelley Creek 71.0
END DESCRIPTION:
XS GIS Cut Line= 3
      1875625.00     13917525.00      1876025.00     13917125.00
      1875791.10     13916305.41
#Sta/Elev= 30
  4438.5 2046.11  4466.8 2043.09  4551.6 2026.66  4594.1 2019.59  4763.8 1998.93
  4792.1 1994.55  4820.3 1987.14  4848.6 1986.66  4862.8 1987.92  4876.9 1987.81
  4933.5 1985.93  4973.9 1981.39  4974.2 1980.89  4977.9 1981.39  5000.7 1984.16
  5060.1 1987.30  5128.9 1988.91  5205.8 1997.20  5239.6 2002.22  5244.8 2001.99
  5305.8 2009.34  5346.3 2016.46  5434.7 2022.65  5497.1 2027.03  5555.3 2032.92
  5603.8 2039.84  5669.7 2047.29  5754.7 2058.78  5804.9 2063.36  5856.5 2066.58
#Mann=5,-1,0
  4438.5     0.1       0  4973.9    0.05       0  4977.9     0.1       0
  5128.9   0.035       0  5434.7     0.1       0
Bank Sta=4973.9,4977.9
Exp/Cntr=0.3,0.1

Type RM Length L Ch R = 1,28938,498,498,498
BEGIN DESCRIPTION:
Kelley Creek 60.0
END DESCRIPTION:
XS GIS Cut Line= 3
      1876324.98     13917475.01      1876725.00     13917225.00
      1877259.64     13916989.82
#Sta/Elev= 30
  4532.2 1997.48  4743.9 1984.29  4779.9 1979.79  4874.2 1979.77  4938.5 1977.30
  4959.7 1974.64  4975.0 1971.14  4988.0 1970.17  4988.4 1969.67  4992.7 1970.17
  4996.3 1971.64  5001.0 1979.96  5006.7 1979.96  5012.9 1987.13  5018.3 1989.36
  5025.8 1997.36  5041.7 2006.55  5047.6 2018.10  5117.2 2034.61  5163.8 2050.09
  5216.0 2060.43  5222.4 2062.79  5255.2 2068.49  5320.7 2087.17  5338.2 2090.44
  5451.8 2096.23  5489.1 2100.70  5512.5 2105.79  5550.2 2110.73  5588.0 2111.94
#Mann=3,-1,0
  4532.2     0.1       0  4988.0    0.05       0  4992.7     0.1       0
Bank Sta=4988,4992.7
Exp/Cntr=0.3,0.1

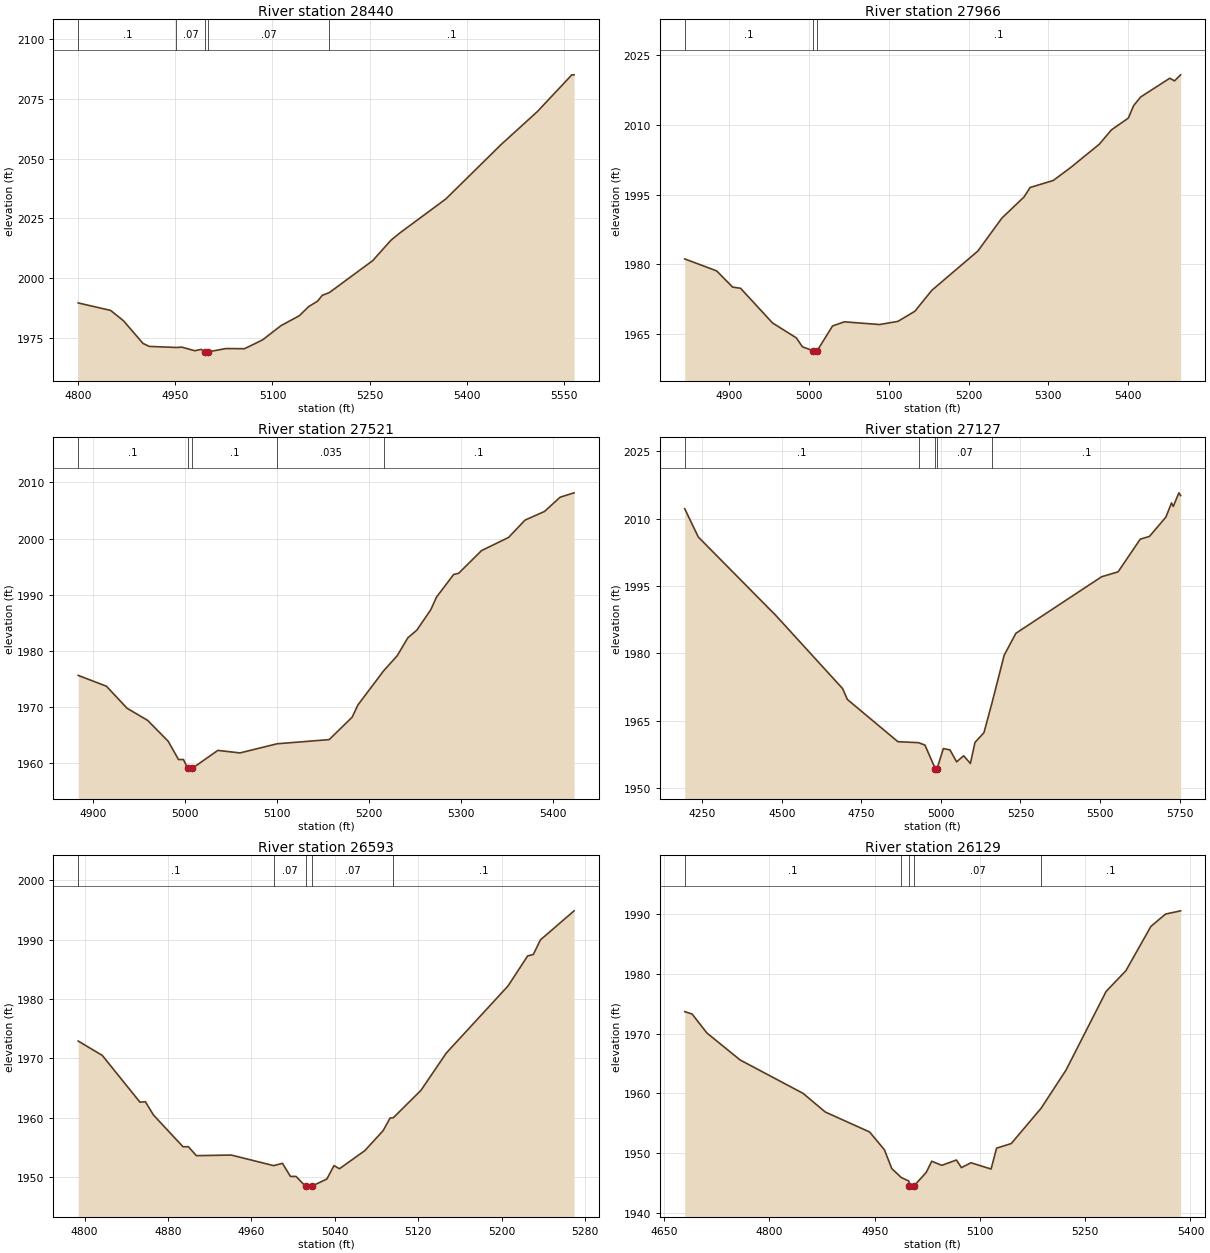
Type RM Length L Ch R = 1,28440,474,474,474
BEGIN DESCRIPTION:
Kelley Creek 59.0
END DESCRIPTION:
XS GIS Cut Line= 3
      1876524.99     13917725.00      1876725.00     13917725.00
      1877125.00     13917325.00
#Sta/Elev= 30
  4800.0 1989.56  4850.0 1986.44  4870.0 1982.09  4900.0 1972.62  4910.0 1971.36
  4951.6 1970.92  4960.0 1971.06  4980.0 1969.55  4990.0 1970.12  4995.2 1969.05
  4995.5 1968.55  4999.9 1969.05  5028.3 1970.47  5056.6 1970.40  5070.7 1972.23
  5084.9 1974.14  5113.1 1980.05  5141.4 1984.20  5155.6 1987.98  5169.7 1990.33
  5176.8 1992.74  5187.9 1993.92  5254.6 2007.24  5282.9 2015.81  5297.0 2018.93
  5367.7 2033.10  5452.6 2055.77  5509.1 2069.71  5562.2 2085.06  5565.7 2085.06
#Mann=5,-1,0
  4800.0     0.1       0  4951.6    0.07       0  4995.2    0.05       0
  4999.9    0.07       0  5187.9     0.1       0
Bank Sta=4995.2,4999.9
Exp/Cntr=0.3,0.1

Type RM Length L Ch R = 1,27966,445,445,445
BEGIN DESCRIPTION:
Kelley Creek 58.0
END DESCRIPTION:
XS GIS Cut Line= 3
      1876925.00     13918224.96      1876925.00     13918075.00
      1877175.02     13917674.97
#Sta/Elev= 30
  4844.2 1981.19  4884.2 1978.62  4904.2 1975.13  4914.2 1974.88  4954.2 1967.43
  4984.2 1964.20  4991.7 1962.30  5005.2 1961.43  5005.6 1960.93  5010.2 1961.43
  5029.5 1966.77  5044.3 1967.66  5088.5 1967.08  5111.5 1967.76  5132.7 1969.93
  5154.0 1974.44  5211.7 1982.88  5241.8 1989.97  5269.5 1994.50  5277.2 1996.55
  5306.1 1998.05  5327.3 2000.74  5363.9 2005.85  5379.2 2008.95  5400.4 2011.48
  5406.9 2014.14  5415.7 2016.00  5452.3 2020.05  5458.2 2019.48  5465.9 2020.78
#Mann=3,-1,0
  4844.2     0.1       0  5005.2    0.05       0  5010.2     0.1       0
Bank Sta=5005.2,5010.2
Exp/Cntr=0.3,0.1

Type RM Length L Ch R = 1,27521,394,394,394
BEGIN DESCRIPTION:
Kelley Creek 57.0
END DESCRIPTION:
XS GIS Cut Line= 3
      1877175.04     13918374.98      1877275.00     13918325.00
      1877425.02     13917924.96
#Sta/Elev= 30
  4883.7 1975.67  4914.4 1973.74  4936.8 1969.82  4959.1 1967.67  4981.5 1963.95
  4992.7 1960.70  4998.1 1960.70  5002.7 1959.13  5003.1 1958.63  5007.7 1959.13
  5035.5 1962.32  5059.5 1961.87  5099.9 1963.50  5156.5 1964.24  5181.5 1968.24
  5187.7 1970.40  5215.9 1976.53  5230.4 1979.16  5242.0 1982.36  5251.8 1983.73
  5266.9 1987.35  5273.1 1989.59  5291.8 1993.63  5297.2 1993.84  5322.1 1997.88
  5351.5 2000.22  5369.3 2003.30  5390.6 2004.85  5407.5 2007.38  5422.7 2008.16
#Mann=5,-1,0
  4883.7     0.1       0  5002.7    0.05       0  5007.7     0.1       0
  5099.9   0.035       0  5215.9     0.1       0
Bank Sta=5002.7,5007.7
Exp/Cntr=0.3,0.1

Type RM Length L Ch R = 1,27127,534,534,534
BEGIN DESCRIPTION:
Kelley Creek 56.1
END DESCRIPTION:
XS GIS Cut Line= 4
      1876926.51     13918995.02      1877478.85     13918625.04
      1877818.30     13918358.00      1878239.08     13918169.68
#Sta/Elev= 30
  4195.3 2012.21  4237.9 2005.91  4482.4 1988.36  4691.2 1972.14  4706.2 1969.72
  4864.9 1960.31  4930.0 1960.09  4949.9 1959.55  4982.6 1954.25  4983.0 1953.75
  4987.6 1954.25  5007.7 1958.78  5028.5 1958.48  5049.3 1955.82  5071.5 1957.17
  5092.6 1955.46  5107.1 1960.16  5135.1 1962.30  5161.5 1969.22  5198.7 1979.56
  5235.4 1984.45  5504.7 1997.05  5556.6 1998.15  5626.2 2005.43  5654.9 2006.03
  5706.7 2010.34  5724.4 2013.51  5729.9 2012.72  5747.6 2015.75  5753.0 2015.13
#Mann=5,-1,0
  4195.3     0.1       0  4930.0    0.07       0  4982.6    0.05       0
  4987.6    0.07       0  5161.5     0.1       0
Bank Sta=4982.6,4987.6
Exp/Cntr=0.3,0.1

Type RM Length L Ch R = 1,26593,464,464,464
BEGIN DESCRIPTION:
Kelley Creek 56.0
END DESCRIPTION:
XS GIS Cut Line= 3
      1877425.04     13919074.99      1877625.00     13919025.00
      1877875.03     13918924.99
#Sta/Elev= 30
  4793.9 1972.93  4817.0 1970.51  4853.1 1962.63  4858.3 1962.71  4866.0 1960.48
  4894.4 1955.12  4899.5 1955.13  4907.2 1953.62  4940.7 1953.72  4981.3 1951.94
  4989.7 1952.33  4997.4 1950.12  5002.7 1950.12  5011.8 1948.48  5012.3 1947.98
  5017.9 1948.48  5032.3 1949.69  5039.1 1951.94  5044.4 1951.42  5068.7 1954.47
  5086.2 1957.83  5092.9 1959.96  5096.0 1960.01  5122.5 1964.63  5146.8 1970.91
  5206.0 1982.22  5224.8 1987.28  5230.2 1987.51  5237.0 1989.97  5269.3 1994.87
#Mann=5,-1,0
  4793.9     0.1       0  4981.3    0.07       0  5011.8    0.05       0
  5017.9    0.07       0  5096.0     0.1       0
Bank Sta=5011.8,5017.9
Exp/Cntr=0.3,0.1

Type RM Length L Ch R = 1,26129,453,453,453
BEGIN DESCRIPTION:
Kelley Creek 55.0
END DESCRIPTION:
XS GIS Cut Line= 3
      1877375.01     13919375.00      1877675.00     13919475.00
      1877974.98     13919225.02
#Sta/Elev= 30
  4679.3 1973.69  4689.8 1973.29  4710.9 1970.11  4758.3 1965.58  4847.9 1959.99
  4879.6 1956.86  4942.8 1953.51  4963.9 1950.52  4974.4 1947.37  4987.8 1945.89
  4998.8 1945.27  4999.6 1944.43  5000.1 1943.93  5005.7 1944.43  5023.5 1946.74
  5031.3 1948.61  5045.6 1947.92  5066.5 1948.81  5073.6 1947.54  5087.3 1948.35
  5115.9 1947.30  5123.7 1950.80  5144.6 1951.57  5187.1 1957.48  5222.7 1963.89
  5279.9 1977.09  5307.9 1980.53  5343.7 1987.99  5364.6 1990.05  5386.0 1990.59
#Mann=5,-1,0
  4679.3     0.1       0  4987.8    0.07       0  4999.6    0.05       0
  5005.7    0.07       0  5187.1     0.1       0
Bank Sta=4999.6,5005.7
Exp/Cntr=0.3,0.1

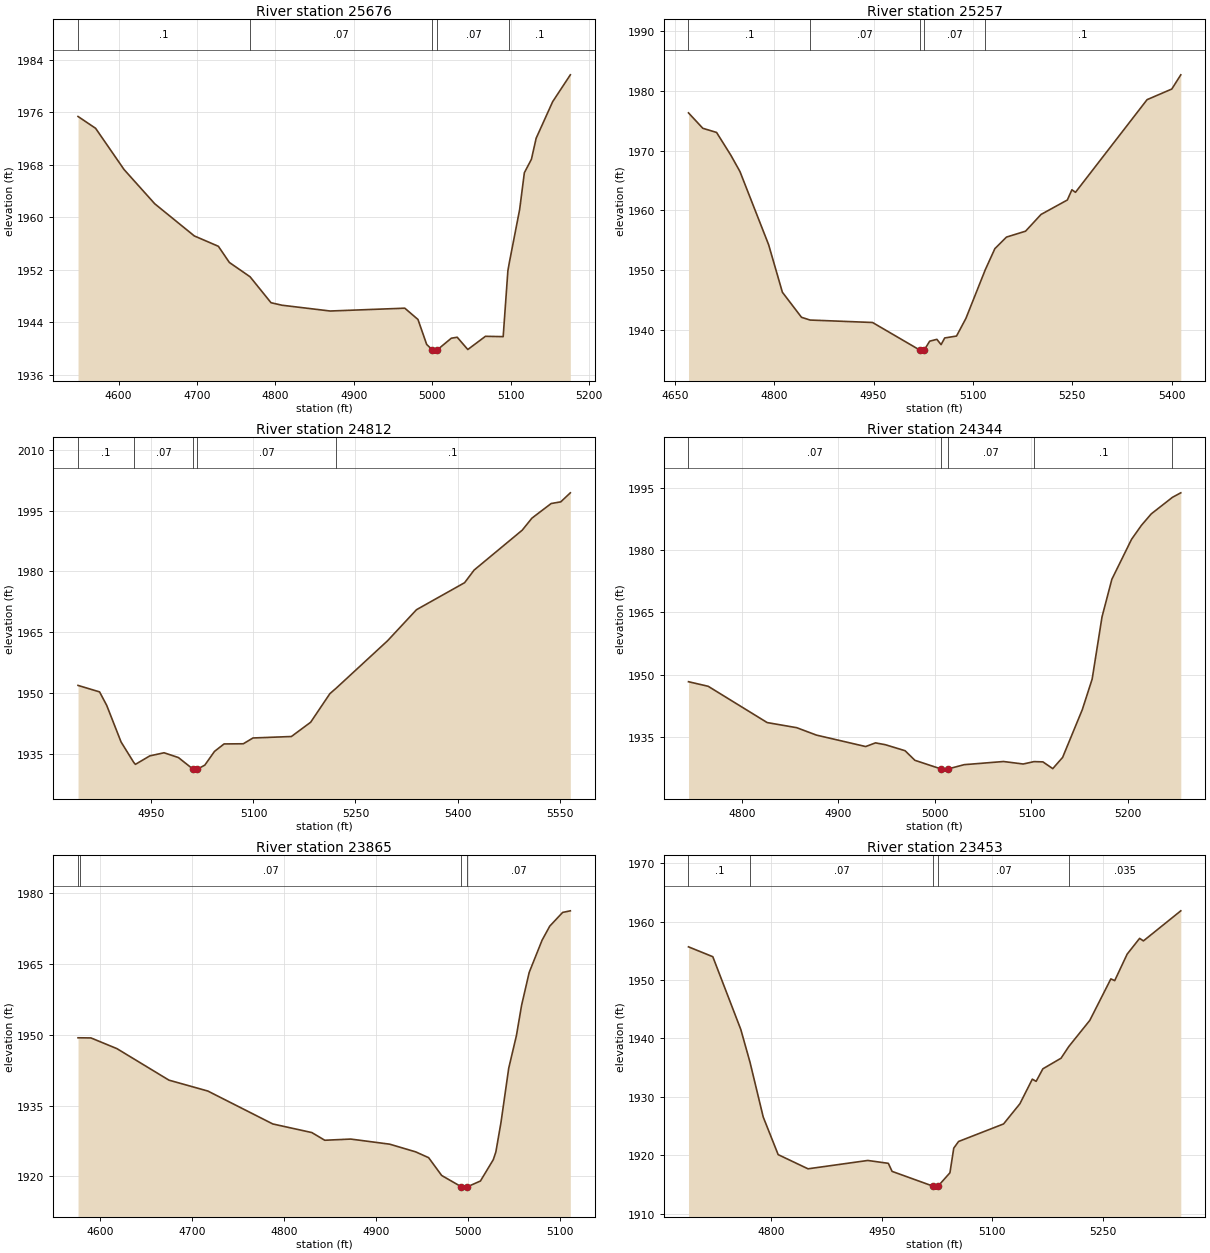
Type RM Length L Ch R = 1,25676,419,419,419
BEGIN DESCRIPTION:
Kelley Creek 54.0
END DESCRIPTION:
XS GIS Cut Line= 3
      1877224.99     13919674.99      1877625.00     13919875.00
      1877775.00     13919975.00
#Sta/Elev= 30
  4548.4 1975.34  4570.8 1973.54  4607.1 1967.26  4646.2 1962.05  4696.6 1957.16
  4727.3 1955.58  4741.3 1953.12  4767.7 1950.94  4794.4 1946.99  4808.4 1946.61
  4869.8 1945.73  4964.9 1946.16  4981.7 1944.44  4992.8 1940.64  5000.0 1939.82
  5000.5 1939.32  5006.3 1939.82  5024.2 1941.59  5031.7 1941.74  5045.2 1939.87
  5067.7 1941.88  5090.3 1941.83  5096.3 1951.86  5098.3 1953.20  5111.3 1961.19
  5117.3 1966.78  5126.3 1968.83  5132.3 1972.02  5153.4 1977.60  5175.9 1981.68
#Mann=5,-1,0
  4548.4     0.1       0  4767.7    0.07       0  5000.0    0.05       0
  5006.3    0.07       0  5098.3     0.1       0
Bank Sta=5000,5006.3
Exp/Cntr=0.3,0.1

Type RM Length L Ch R = 1,25257,445,445,445
BEGIN DESCRIPTION:
Kelley Creek 53.0
END DESCRIPTION:
XS GIS Cut Line= 3
      1877074.99     13919874.99      1877325.00     13920075.00
      1877711.54     13920245.90
#Sta/Elev= 30
  4670.8 1976.34  4692.4 1973.76  4713.2 1973.06  4734.8 1969.23  4748.4 1966.53
  4791.7 1954.27  4812.5 1946.30  4841.3 1942.11  4854.2 1941.65  4948.5 1941.24
  5020.0 1936.61  5020.5 1936.11  5026.4 1936.61  5034.7 1938.11  5045.6 1938.42
  5051.9 1937.53  5057.4 1938.65  5075.2 1938.97  5089.4 1941.93  5118.6 1950.07
  5133.1 1953.61  5150.6 1955.54  5179.4 1956.53  5202.7 1959.33  5242.4 1961.75
  5249.3 1963.46  5254.7 1963.04  5362.7 1978.55  5400.0 1980.33  5413.6 1982.71
#Mann=5,-1,0
  4670.8     0.1       0  4854.2    0.07       0  5020.0    0.05       0
  5026.4    0.07       0  5118.6     0.1       0
Bank Sta=5020,5026.4
Exp/Cntr=0.3,0.1

Type RM Length L Ch R = 1,24812,468,468,468
BEGIN DESCRIPTION:
Kelley Creek 52.0
END DESCRIPTION:
XS GIS Cut Line= 3
      1876974.96     13920374.99      1877125.00     13920425.00
      1877524.97     13920824.97
#Sta/Elev= 30
  4842.1 1951.86  4873.8 1950.26  4884.3 1946.92  4905.4 1937.90  4923.9 1932.89
  4926.5 1932.38  4947.6 1934.47  4968.6 1935.24  4989.7 1934.06  5011.1 1931.21
  5011.6 1930.71  5017.6 1931.21  5028.5 1932.19  5042.7 1935.57  5056.8 1937.42
  5085.1 1937.46  5099.3 1938.89  5155.8 1939.25  5184.1 1942.77  5212.4 1949.83
  5221.6 1951.17  5297.2 1962.88  5339.7 1970.54  5410.4 1977.20  5424.5 1980.33
  5495.2 1990.17  5509.4 1993.13  5537.7 1996.74  5551.8 1997.15  5565.9 1999.38
#Mann=5,-1,0
  4842.1     0.1       0  4923.9    0.07       0  5011.1    0.05       0
  5017.6    0.07       0  5221.6     0.1       0
Bank Sta=5011.1,5017.6
Exp/Cntr=0.3,0.1

Type RM Length L Ch R = 1,24344,479,479,479
BEGIN DESCRIPTION:
Kelley Creek 51.0
END DESCRIPTION:
XS GIS Cut Line= 3
      1876875.01     13920575.04      1876925.00     13920825.00
      1876975.01     13921075.03
#Sta/Elev= 30
  4744.8 1948.36  4765.2 1947.26  4826.3 1938.54  4856.9 1937.31  4877.3 1935.53
  4928.3 1932.78  4938.5 1933.66  4948.7 1933.22  4969.1 1931.78  4979.3 1929.47
  5006.7 1927.37  5007.2 1926.87  5012.7 1926.87  5013.2 1927.37  5030.3 1928.42
  5071.1 1929.18  5091.5 1928.58  5102.7 1929.16  5111.9 1929.09  5122.1 1927.47
  5132.3 1930.17  5152.7 1941.66  5162.9 1949.00  5173.1 1963.94  5183.3 1972.98
  5203.7 1982.59  5213.9 1985.94  5224.1 1988.70  5246.1 1992.69  5254.7 1993.76
#Mann=5,-1,0
  4744.8    0.07       0  5006.7    0.05       0  5013.2    0.07       0
  5102.7     0.1       0  5246.1    0.07       0
Bank Sta=5006.7,5013.2
Exp/Cntr=0.3,0.1

Type RM Length L Ch R = 1,23865,412,412,412
BEGIN DESCRIPTION:
Kelley Creek 50.0
END DESCRIPTION:
XS GIS Cut Line= 3
      1876825.00     13920525.00      1876525.00     13920825.00
      1876424.97     13920875.02
#Sta/Elev= 30
  4575.7 1949.35  4577.5 1949.35  4589.8 1949.32  4618.1 1947.05  4674.7 1940.38
  4717.1 1938.07  4787.8 1931.10  4830.3 1929.28  4844.4 1927.65  4872.7 1927.90
  4915.1 1926.82  4943.4 1925.19  4957.5 1923.96  4971.7 1920.19  4993.1 1917.80
  4993.6 1917.30  4999.2 1917.30  4999.7 1917.80  5013.9 1919.02  5027.9 1923.54
  5030.7 1925.18  5036.3 1931.45  5044.7 1942.91  5053.1 1949.83  5058.7 1956.22
  5067.0 1963.20  5081.0 1970.01  5089.4 1973.00  5103.4 1975.90  5111.8 1976.24
#Mann=4,-1,0
  4575.7     0.1       0  4577.5    0.07       0  4993.1    0.05       0
  4999.7    0.07       0
Bank Sta=4993.1,4999.7
Exp/Cntr=0.3,0.1

Type RM Length L Ch R = 1,23453,452,452,452
BEGIN DESCRIPTION:
Kelley Creek 49.0
END DESCRIPTION:
XS GIS Cut Line= 3
      1876375.00     13920175.00      1876325.00     13920475.00
      1876225.01     13920824.96
#Sta/Elev= 30
  4687.6 1955.70  4720.6 1954.01  4758.6 1941.54  4771.1 1935.92  4789.0 1926.55
  4809.3 1920.10  4849.8 1917.67  4930.9 1919.10  4958.8 1918.61  4963.9 1917.23
  5019.6 1914.69  5020.1 1914.19  5026.2 1914.69  5042.4 1916.99  5047.6 1921.21
  5054.1 1922.35  5115.2 1925.36  5137.3 1928.81  5154.2 1933.03  5159.4 1932.66
  5168.5 1934.80  5193.2 1936.62  5203.7 1938.62  5232.2 1943.10  5260.8 1950.21
  5266.0 1949.91  5282.9 1954.45  5299.8 1957.15  5305.0 1956.72  5355.7 1961.87
#Mann=5,-1,0
  4687.6     0.1       0  4771.1    0.07       0  5019.6    0.05       0
  5026.2    0.07       0  5203.7   0.035       0
Bank Sta=5019.6,5026.2
Exp/Cntr=0.3,0.1

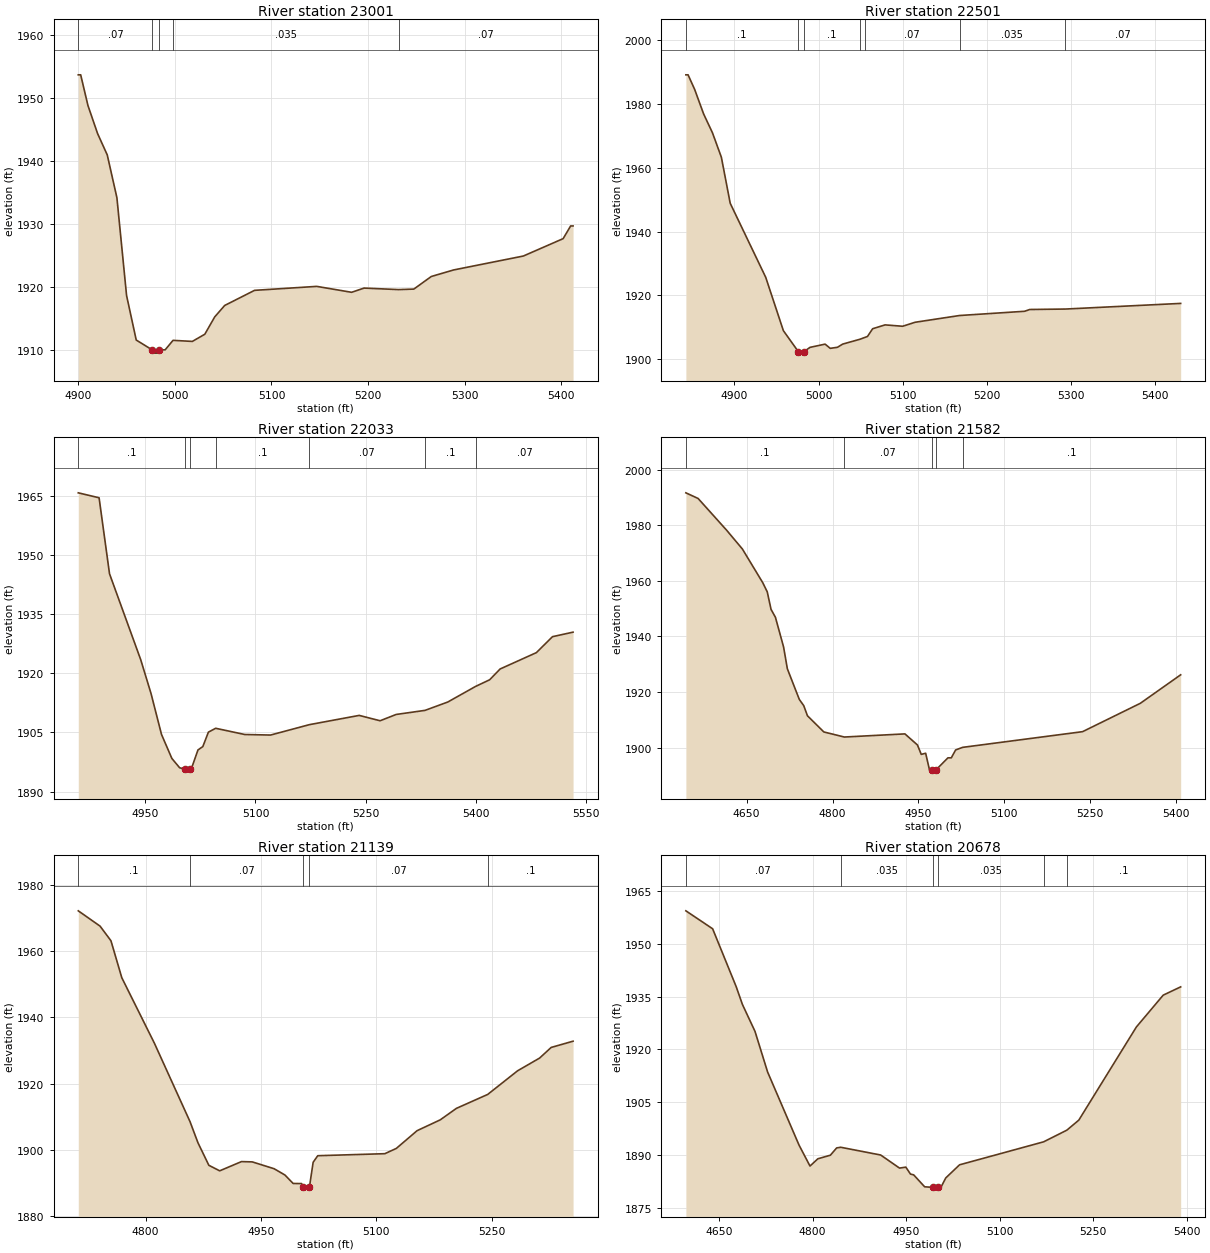
Type RM Length L Ch R = 1,23001,500,500,500
BEGIN DESCRIPTION:
Kelley Creek 48.0
END DESCRIPTION:
XS GIS Cut Line= 3
      1876025.00     13920124.97      1876025.00     13920225.00
      1876124.99     13920624.96
#Sta/Elev= 30
  4900.0 1953.64  4902.5 1953.64  4910.0 1948.77  4920.0 1944.31  4930.0 1940.92
  4940.0 1934.12  4950.0 1918.59  4960.0 1911.52  4976.7 1909.94  4977.2 1909.44
  4982.9 1909.44  4983.4 1909.94  4990.0 1909.97  4998.1 1911.47  5018.1 1911.30
  5031.0 1912.44  5041.3 1915.20  5051.6 1917.01  5082.5 1919.41  5146.9 1920.04
  5183.0 1919.10  5195.9 1919.77  5231.7 1919.53  5247.4 1919.61  5265.5 1921.61
  5288.6 1922.65  5360.8 1924.86  5402.0 1927.62  5409.8 1929.64  5412.3 1929.64
#Mann=5,-1,0
  4900.0    0.07       0  4976.7   0.035       0  4983.4    0.07       0
  4998.1   0.035       0  5231.7    0.07       0
Bank Sta=4976.7,4983.4
Exp/Cntr=0.3,0.1

Type RM Length L Ch R = 1,22501,468,468,468
BEGIN DESCRIPTION:
Kelley Creek 47.0
END DESCRIPTION:
XS GIS Cut Line= 3
      1875475.00     13920075.00      1875525.00     13920225.00
      1875874.98     13920474.98
#Sta/Elev= 30
  4842.3 1989.19  4844.9 1989.19  4852.8 1984.57  4863.4 1976.91  4873.9 1971.01
  4884.5 1963.32  4895.0 1948.89  4937.2 1925.67  4958.2 1908.92  4975.9 1902.37
  4976.4 1901.87  4982.2 1901.87  4982.7 1902.37  4989.9 1903.68  5007.8 1904.69
  5013.9 1903.37  5022.5 1903.70  5028.7 1904.70  5049.2 1906.22  5055.0 1906.79
  5058.2 1907.10  5064.3 1909.52  5079.1 1910.73  5100.0 1910.30  5114.7 1911.55
  5167.6 1913.67  5245.0 1915.00  5251.1 1915.56  5293.4 1915.70  5430.5 1917.47
#Mann=7,-1,0
  4842.3     0.1       0  4975.9    0.05       0  4982.7     0.1       0
  5049.2   0.035       0  5055.0    0.07       0  5167.6   0.035       0
  5293.4    0.07       0
Bank Sta=4975.9,4982.7
Exp/Cntr=0.3,0.1

Type RM Length L Ch R = 1,22033,451,451,451
BEGIN DESCRIPTION:
Kelley Creek 46.0
END DESCRIPTION:
XS GIS Cut Line= 3
      1875124.98     13920424.98      1875225.00     13920525.00
      1875625.03     13920875.03
#Sta/Elev= 30
  4859.0 1965.85  4887.3 1964.59  4901.5 1945.29  4943.9 1923.49  4958.0 1914.86
  4972.2 1904.50  4986.3 1898.40  4996.9 1896.03  5004.2 1895.68  5004.7 1895.18
  5011.0 1895.68  5014.2 1896.52  5021.8 1900.56  5028.4 1901.41  5036.0 1905.08
  5045.9 1906.06  5085.4 1904.48  5120.5 1904.34  5173.3 1906.98  5241.1 1909.33
  5269.5 1907.97  5291.4 1909.57  5330.7 1910.61  5361.6 1912.73  5399.5 1916.70
  5418.5 1918.37  5432.8 1921.12  5482.1 1925.27  5504.0 1929.32  5532.0 1930.47
#Mann=7,-1,0
  4859.0     0.1       0  5004.2    0.05       0  5011.0     0.1       0
  5045.9     0.1       0  5173.3    0.07       0  5330.7     0.1       0
  5399.5    0.07       0
Bank Sta=5004.2,5011
Exp/Cntr=0.3,0.1

Type RM Length L Ch R = 1,21582,443,443,443
BEGIN DESCRIPTION:
Kelley Creek 45.0
END DESCRIPTION:
XS GIS Cut Line= 3
      1874875.03     13921274.97      1875175.00     13920925.00
      1875574.95     13920974.99
#Sta/Elev= 30
  4543.9 1991.73  4565.3 1989.69  4614.7 1978.35  4642.6 1971.49  4678.3 1959.31
  4686.0 1956.06  4692.6 1949.77  4700.3 1946.89  4714.5 1936.23  4721.1 1928.36
  4742.0 1917.31  4749.7 1915.09  4756.2 1911.43  4784.8 1905.61  4820.6 1903.78
  4926.4 1904.91  4948.3 1900.91  4954.9 1897.53  4962.6 1897.94  4969.2 1892.04
  4972.8 1892.00  4973.3 1891.50  4980.9 1892.00  5001.5 1896.29  5007.4 1896.29
  5014.9 1899.12  5027.1 1900.06  5236.6 1905.71  5337.4 1915.92  5407.9 1926.19
#Mann=5,-1,0
  4543.9     0.1       0  4820.6    0.07       0  4972.8    0.05       0
  4980.9    0.07       0  5027.1     0.1       0
Bank Sta=4972.8,4980.9
Exp/Cntr=0.3,0.1

Type RM Length L Ch R = 1,21139,461,461,461
BEGIN DESCRIPTION:
Kelley Creek 44.0
END DESCRIPTION:
XS GIS Cut Line= 3
      1875174.97     13921475.03      1875375.00     13921275.00
      1875674.96     13921075.03
#Sta/Elev= 30
  4712.4 1972.21  4740.7 1967.59  4754.9 1963.16  4769.0 1951.99  4811.4 1932.19
  4857.7 1908.50  4868.0 1902.13  4882.2 1895.30  4896.3 1893.63  4924.6 1896.42
  4938.7 1896.33  4967.0 1894.27  4981.1 1892.37  4991.8 1889.81  5002.8 1889.78
  5004.7 1888.60  5005.2 1888.10  5012.9 1888.60  5017.8 1896.21  5023.8 1898.20
  5111.0 1898.81  5126.0 1900.41  5153.0 1905.77  5183.1 1909.04  5204.1 1912.51
  5244.8 1916.72  5283.7 1923.87  5312.3 1927.71  5327.3 1930.92  5355.8 1932.81
#Mann=5,-1,0
  4712.4     0.1       0  4857.7    0.07       0  5004.7    0.05       0
  5012.9    0.07       0  5244.8     0.1       0
Bank Sta=5004.7,5012.9
Exp/Cntr=0.3,0.1

Type RM Length L Ch R = 1,20678,446,446,446
BEGIN DESCRIPTION:
Kelley Creek 43.0
END DESCRIPTION:
XS GIS Cut Line= 3
      1875274.96     13921625.01      1875675.00     13921575.00
      1875925.02     13921274.98
#Sta/Elev= 30
  4596.8 1959.33  4639.7 1954.24  4677.5 1937.81  4687.5 1932.76  4707.7 1925.11
  4727.9 1913.59  4778.2 1892.89  4795.9 1886.90  4808.5 1888.96  4828.6 1889.98
  4838.7 1892.05  4845.2 1892.23  4909.3 1890.03  4939.5 1886.32  4949.6 1886.59
  4957.1 1884.62  4962.2 1884.40  4979.8 1881.01  4993.3 1880.85  4993.8 1880.35
  5001.5 1880.85  5007.1 1881.27  5013.6 1883.51  5035.8 1887.25  5170.6 1893.77
  5207.8 1897.07  5227.1 1899.93  5319.5 1926.38  5362.5 1935.40  5390.5 1937.75
#Mann=6,-1,0
  4596.8    0.07       0  4845.2   0.035       0  4993.3   0.035       0
  5001.5   0.035       0  5170.6    0.07       0  5207.8     0.1       0
Bank Sta=4993.3,5001.5
Exp/Cntr=0.3,0.1