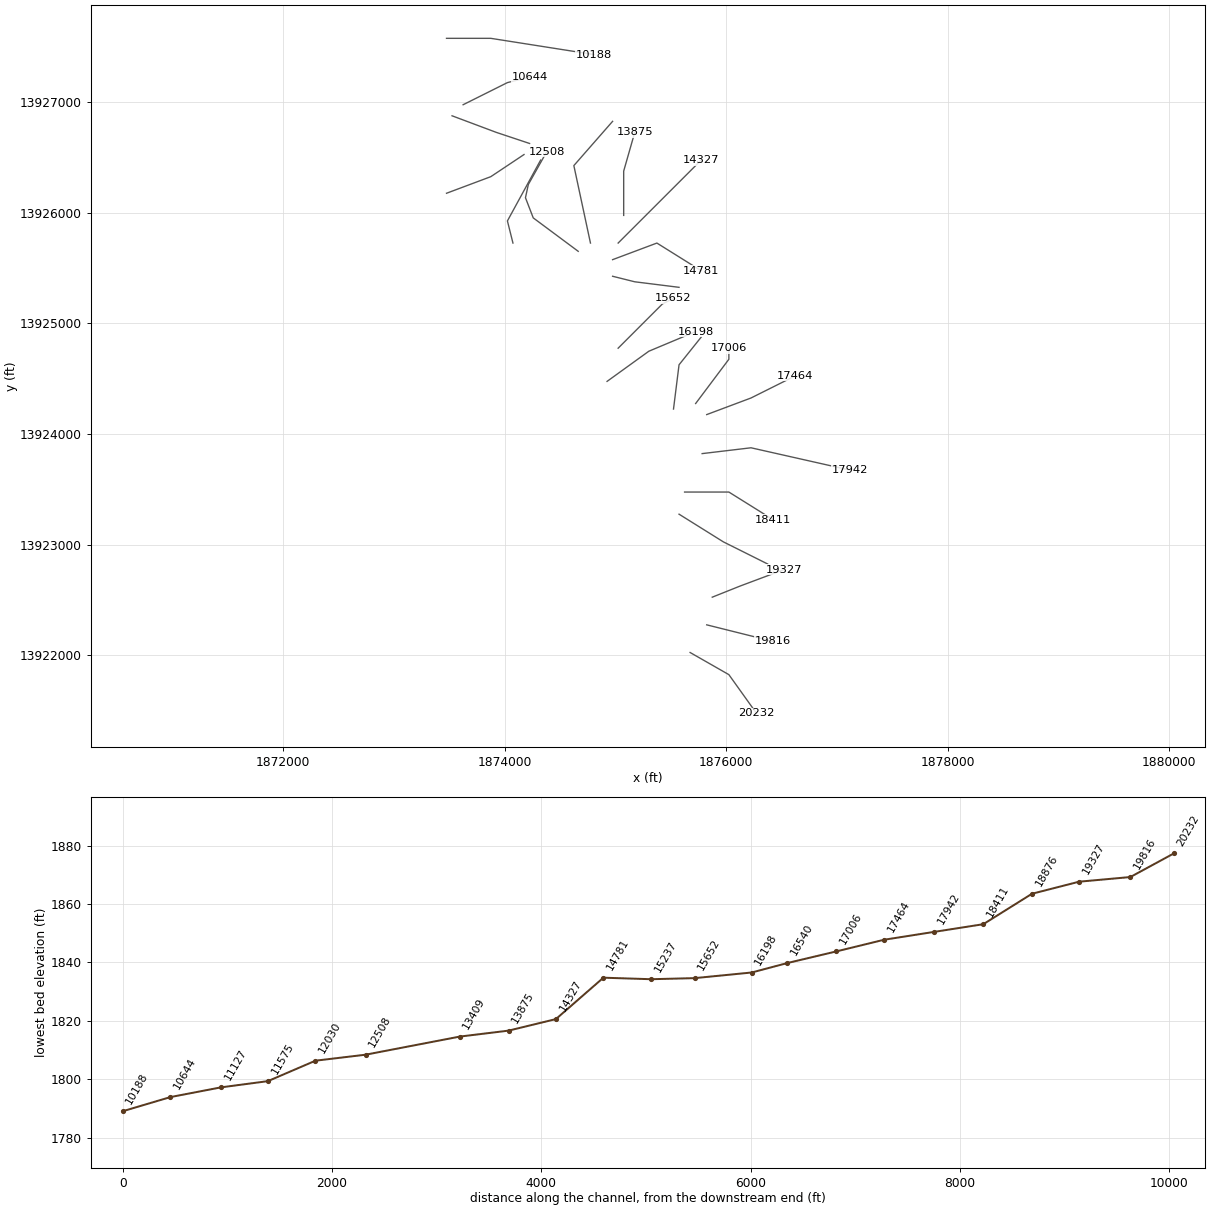
HEC-RAS study Kelley Creek.prj: Kelley Creek Base Level Engineering

--- Kelley Creek.g01 (geometry) --- (continued)

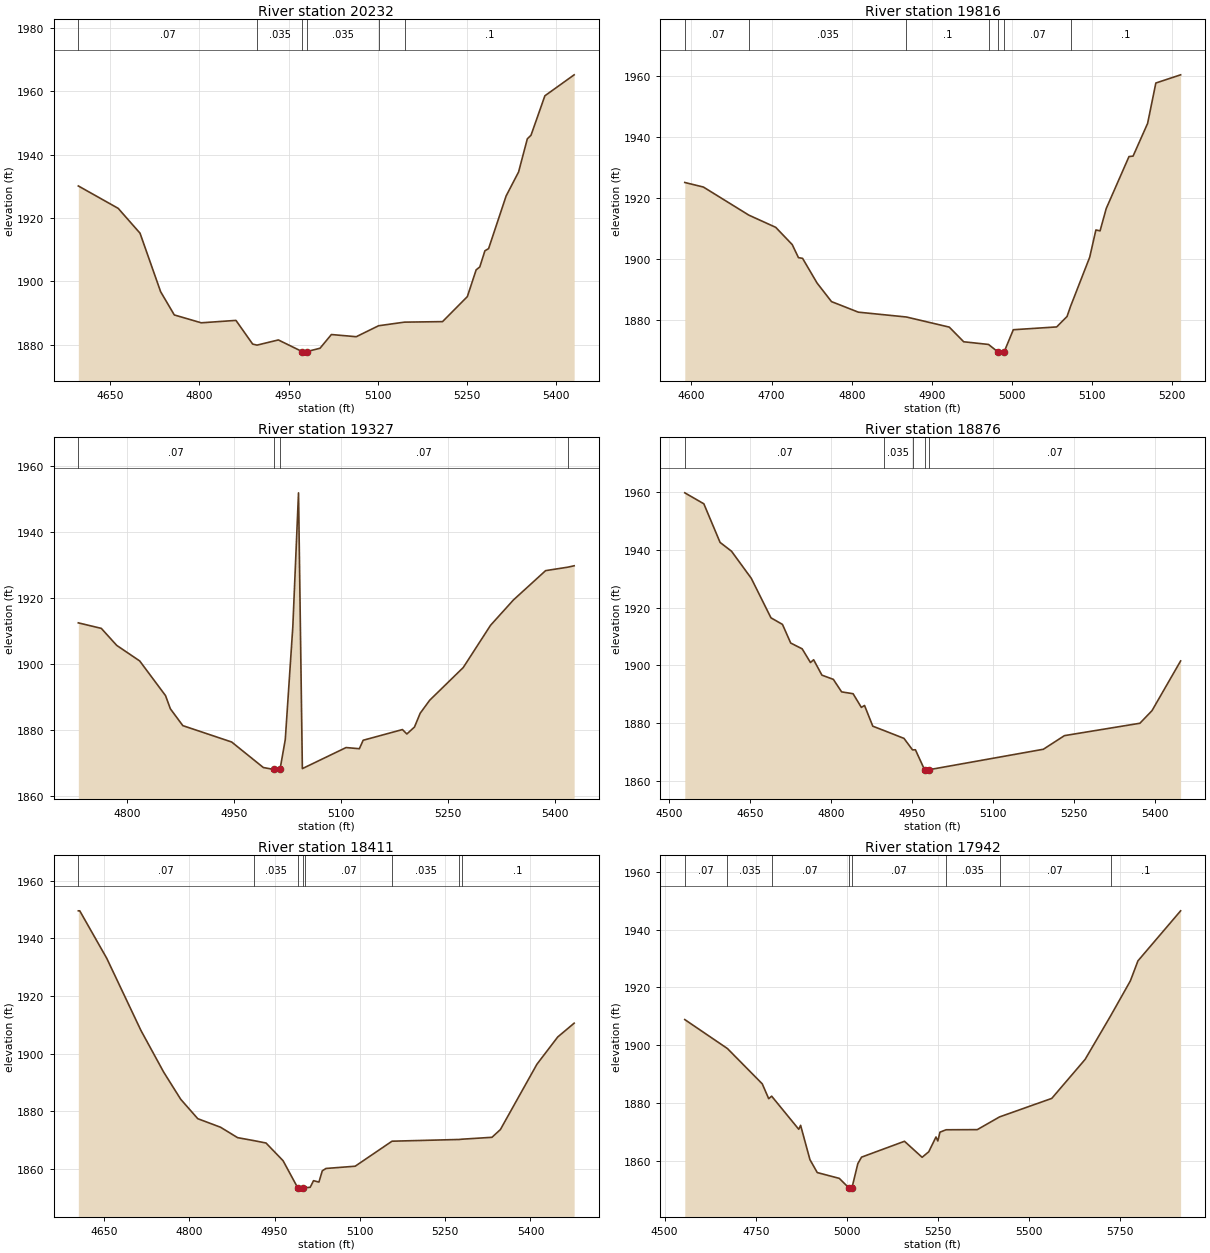
Type RM Length L Ch R = 1,20232,416,416,416
BEGIN DESCRIPTION:
Kelley Creek 42.0
END DESCRIPTION:
XS GIS Cut Line= 3
      1875674.97     13922025.02      1876025.00     13921825.00
      1876275.02     13921474.98
#Sta/Elev= 30
  4596.6 1930.11  4663.6 1923.04  4700.3 1915.20  4734.9 1896.74  4757.9 1889.40
  4803.2 1886.92  4861.5 1887.68  4889.6 1880.20  4897.0 1879.88  4932.8 1881.51
  4972.6 1877.85  4973.1 1877.35  4980.9 1877.85  5002.8 1878.89  5021.9 1883.22
  5063.7 1882.53  5101.2 1885.99  5144.8 1887.13  5208.7 1887.29  5250.4 1895.19
  5265.2 1903.63  5271.3 1904.55  5279.9 1909.65  5286.1 1910.33  5315.6 1926.97
  5336.5 1934.52  5351.2 1944.98  5357.4 1946.12  5380.7 1958.56  5429.9 1965.18
#Mann=6,-1,0
  4596.6    0.07       0  4897.0   0.035       0  4972.6   0.035       0
  4980.9   0.035       0  5101.2    0.07       0  5144.8     0.1       0
Bank Sta=4972.6,4980.9
Exp/Cntr=0.3,0.1

Type RM Length L Ch R = 1,19816,489,489,489
BEGIN DESCRIPTION:
Kelley Creek 41.0
END DESCRIPTION:
XS GIS Cut Line= 3
      1875824.96     13922275.01      1876225.00     13922175.00
      1876425.00     13922125.00
#Sta/Elev= 30
  4591.8 1925.12  4615.0 1923.63  4671.7 1914.43  4705.2 1910.44  4725.8 1904.79
  4733.6 1900.51  4738.7 1900.29  4756.8 1892.20  4774.8 1886.12  4808.3 1882.66
  4868.2 1881.08  4921.7 1877.77  4939.7 1872.97  4970.7 1872.09  4981.9 1869.75
  4982.4 1869.25  4990.3 1869.75  5001.6 1876.91  5055.7 1877.83  5068.6 1881.25
  5073.1 1884.63  5096.9 1900.66  5104.6 1909.57  5109.8 1909.28  5117.5 1916.59
  5145.9 1933.61  5151.0 1933.76  5169.1 1944.45  5179.4 1957.69  5210.3 1960.37
#Mann=7,-1,0
  4591.8    0.07       0  4671.7   0.035       0  4868.2     0.1       0
  4970.7    0.07       0  4981.9    0.05       0  4990.3    0.07       0
  5073.1     0.1       0
Bank Sta=4981.9,4990.3
Exp/Cntr=0.3,0.1

Type RM Length L Ch R = 1,19327,451,451,451
BEGIN DESCRIPTION:
Kelley Creek 40.0
END DESCRIPTION:
XS GIS Cut Line= 3
      1875874.97     13922524.99      1876125.00     13922625.00
      1876525.01     13922775.00
#Sta/Elev= 30
  4731.0 1912.57  4763.3 1910.90  4784.9 1905.75  4817.2 1901.04  4853.5 1890.53
  4860.3 1886.54  4877.8 1881.44  4946.4 1876.48  4990.9 1868.75  5005.8 1868.16
  5006.3 1867.66  5014.3 1868.16  5021.7 1877.21  5032.3 1911.40  5040.3 1951.96
  5045.7 1868.42  5107.1 1874.80  5125.8 1874.45  5131.1 1877.01  5186.3 1880.25
  5192.5 1878.91  5203.2 1881.02  5211.2 1885.19  5224.6 1889.14  5271.7 1899.04
  5310.0 1911.82  5342.1 1919.49  5387.4 1928.39  5418.6 1929.44  5427.5 1929.86
#Mann=4,-1,0
  4731.0    0.07       0  5005.8    0.05       0  5014.3    0.07       0
  5418.6     0.1       0
Bank Sta=5005.8,5014.3
Exp/Cntr=0.3,0.1

Type RM Length L Ch R = 1,18876,465,465,465
BEGIN DESCRIPTION:
Kelley Creek 39.0
END DESCRIPTION:
XS GIS Cut Line= 3
      1875575.04     13923274.98      1875975.00     13923025.00
      1876375.03     13922824.99
#Sta/Elev= 30
  4528.8 1959.63  4564.1 1955.84  4594.2 1942.50  4615.4 1939.46  4652.0 1930.11
  4688.5 1916.46  4709.8 1914.19  4725.1 1907.75  4746.3 1905.76  4761.7 1901.03
  4767.6 1901.98  4782.9 1896.67  4804.1 1895.21  4819.4 1890.89  4840.7 1890.25
  4856.0 1885.53  4861.9 1886.19  4877.2 1879.04  4898.3 1877.52  4935.0 1874.83
  4950.9 1870.85  4956.2 1870.90  4973.1 1864.02  4973.6 1863.52  4981.8 1864.02
  5193.3 1871.07  5232.4 1875.78  5372.2 1880.05  5394.6 1884.39  5447.7 1901.57
#Mann=5,-1,0
  4528.8    0.07       0  4898.3   0.035       0  4950.9    0.07       0
  4973.1    0.05       0  4981.8    0.07       0
Bank Sta=4973.1,4981.8
Exp/Cntr=0.3,0.1

Type RM Length L Ch R = 1,18411,469,469,469
BEGIN DESCRIPTION:
Kelley Creek 38.0
END DESCRIPTION:
XS GIS Cut Line= 3
      1875625.02     13923475.00      1876025.00     13923475.00
      1876425.02     13923224.99
#Sta/Elev= 30
  4605.1 1949.54  4607.6 1949.54  4655.1 1933.07  4715.1 1908.11  4755.1 1893.66
  4785.1 1884.23  4815.1 1877.50  4855.1 1874.54  4885.1 1870.93  4914.3 1869.88
  4935.1 1869.07  4965.1 1862.93  4990.7 1853.59  4991.2 1853.09  4999.4 1853.59
  5004.0 1853.59  5012.7 1853.72  5018.6 1856.02  5028.1 1855.53  5034.0 1859.44
  5040.5 1860.25  5091.8 1861.03  5156.6 1869.70  5275.2 1870.30  5279.4 1870.39
  5332.3 1871.05  5347.1 1873.73  5411.3 1896.36  5447.9 1905.82  5476.8 1910.60
#Mann=8,-1,0
  4605.1    0.07       0  4914.3   0.035       0  4990.7   0.035       0
  4999.4   0.035       0  5004.0    0.07       0  5156.6   0.035       0
  5275.2    0.07       0  5279.4     0.1       0
Bank Sta=4990.7,4999.4
Exp/Cntr=0.3,0.1

Type RM Length L Ch R = 1,17942,478,478,478
BEGIN DESCRIPTION:
Kelley Creek 37.0
END DESCRIPTION:
XS GIS Cut Line= 3
      1875783.82     13923822.42      1876225.00     13923875.00
      1877119.60     13923673.12
#Sta/Elev= 30
  4555.3 1908.93  4672.4 1898.94  4768.0 1886.77  4785.7 1881.65  4793.8 1882.52
  4868.2 1871.10  4873.3 1872.46  4898.9 1860.64  4919.0 1856.17  4979.5 1854.17
  5005.3 1850.96  5005.8 1850.46  5014.4 1850.96  5030.4 1859.25  5040.6 1861.49
  5158.5 1866.96  5206.9 1861.44  5225.1 1863.34  5245.0 1868.44  5250.1 1867.07
  5255.9 1870.11  5272.7 1870.93  5358.4 1870.98  5419.4 1875.36  5562.9 1881.75
  5654.4 1895.19  5724.2 1910.15  5778.7 1922.28  5799.5 1929.18  5916.7 1946.44
#Mann=8,-1,0
  4555.3    0.07       0  4672.4   0.035       0  4793.8    0.07       0
  5005.3    0.05       0  5014.4    0.07       0  5272.7   0.035       0
  5419.4    0.07       0  5724.2     0.1       0
Bank Sta=5005.3,5014.4
Exp/Cntr=0.3,0.1

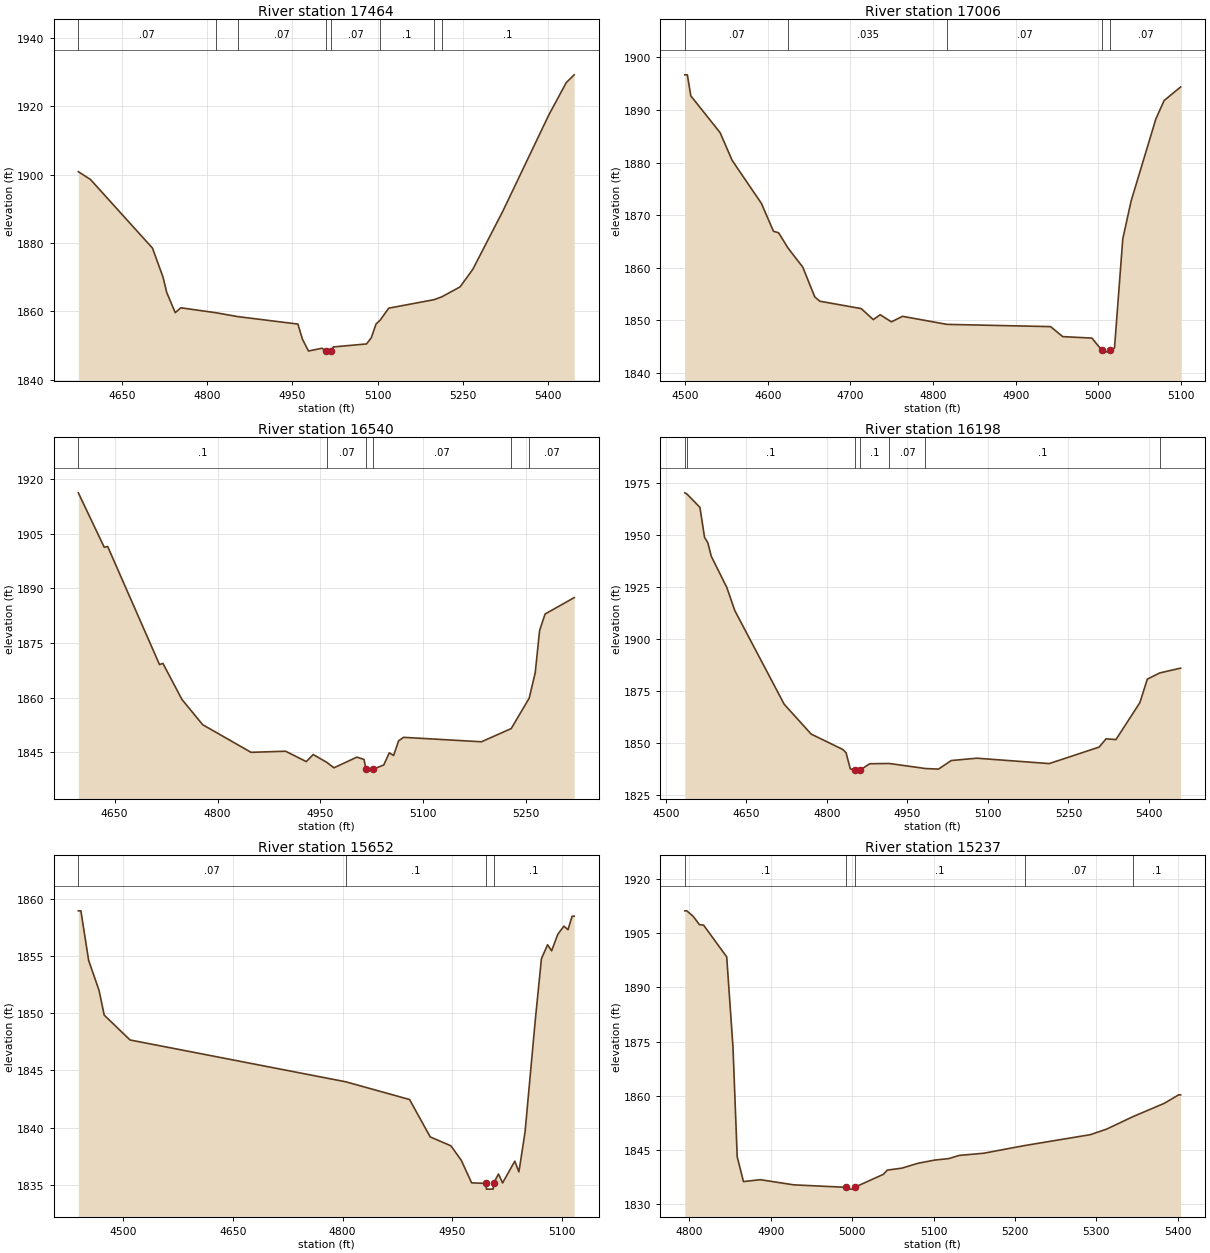
Type RM Length L Ch R = 1,17464,458,458,458
BEGIN DESCRIPTION:
Kelley Creek 36.0
END DESCRIPTION:
XS GIS Cut Line= 3
      1875824.99     13924174.99      1876225.00     13924325.00
      1876624.97     13924524.99
#Sta/Elev= 30
  4572.4 1900.85  4593.8 1898.57  4703.2 1878.48  4721.9 1869.93  4728.2 1865.55
  4743.3 1859.60  4753.1 1861.03  4814.9 1859.59  4853.7 1858.45  4959.6 1856.27
  4967.6 1851.85  4978.3 1848.39  5002.4 1849.21  5008.9 1848.27  5009.4 1847.77
  5018.2 1848.27  5022.0 1849.58  5080.7 1850.46  5089.1 1852.28  5097.4 1856.28
  5104.9 1857.47  5119.8 1860.92  5199.8 1863.41  5213.3 1864.23  5245.6 1867.15
  5267.9 1872.24  5321.1 1889.32  5402.1 1917.44  5432.9 1926.91  5446.8 1929.18
#Mann=8,-1,0
  4572.4    0.07       0  4814.9   0.035       0  4853.7    0.07       0
  5008.9    0.05       0  5018.2    0.07       0  5104.9     0.1       0
  5199.8    0.07       0  5213.3     0.1       0
Bank Sta=5008.9,5018.2
Exp/Cntr=0.3,0.1

Type RM Length L Ch R = 1,17006,466,466,466
BEGIN DESCRIPTION:
Kelley Creek 35.0
END DESCRIPTION:
XS GIS Cut Line= 3
      1875725.02     13924275.02      1876025.00     13924675.00
      1876025.00     13924775.03
#Sta/Elev= 30
  4499.6 1896.69  4502.7 1896.69  4506.9 1892.68  4542.3 1885.70  4556.9 1880.42
  4592.3 1872.24  4606.9 1866.94  4613.1 1866.65  4624.6 1863.73  4642.3 1860.13
  4656.9 1854.45  4663.1 1853.63  4713.1 1852.23  4727.7 1850.13  4736.0 1851.07
  4749.6 1849.71  4763.1 1850.76  4816.8 1849.23  4942.3 1848.80  4956.9 1846.90
  4992.3 1846.62  5004.5 1844.26  5005.0 1843.76  5014.6 1844.26  5019.6 1844.75
  5029.6 1865.47  5039.6 1872.64  5069.6 1888.28  5079.6 1891.80  5099.6 1894.38
#Mann=5,-1,0
  4499.6    0.07       0  4624.6   0.035       0  4816.8    0.07       0
  5004.5    0.05       0  5014.6    0.07       0
Bank Sta=5004.5,5014.6
Exp/Cntr=0.3,0.1

Type RM Length L Ch R = 1,16540,342,342,342
BEGIN DESCRIPTION:
Kelley Creek 34.0
END DESCRIPTION:
XS GIS Cut Line= 3
      1875525.00     13924225.04      1875575.00     13924625.00
      1875774.98     13924874.97
#Sta/Elev= 30
  4597.0 1916.29  4634.8 1901.32  4639.8 1901.54  4715.4 1869.08  4720.4 1869.40
  4748.1 1859.50  4778.4 1852.55  4848.9 1844.96  4899.3 1845.26  4929.5 1842.41
  4939.6 1844.35  4959.2 1842.23  4969.8 1840.70  5003.3 1843.64  5013.7 1842.99
  5016.6 1840.29  5017.1 1839.79  5026.7 1840.29  5042.5 1841.48  5050.5 1844.81
  5056.9 1844.10  5064.1 1848.10  5071.3 1849.08  5185.0 1847.86  5228.4 1851.49
  5254.6 1859.83  5263.4 1866.83  5269.8 1878.43  5277.8 1882.98  5320.2 1887.48
#Mann=6,-1,0
  4597.0     0.1       0  4959.2    0.07       0  5016.6    0.05       0
  5026.7    0.07       0  5228.4     0.1       0  5254.6    0.07       0
Bank Sta=5016.6,5026.7
Exp/Cntr=0.3,0.1

Type RM Length L Ch R = 1,16198,546,546,546
BEGIN DESCRIPTION:
Kelley Creek 33.0
END DESCRIPTION:
XS GIS Cut Line= 3
      1874925.01     13924475.00      1875302.33     13924747.62
      1875725.02     13924925.01
#Sta/Elev= 30
  4535.1 1970.39  4539.1 1969.82  4563.3 1963.40  4571.9 1948.96  4578.0 1946.40
  4584.4 1939.91  4613.6 1924.74  4628.3 1913.74  4720.3 1868.71  4770.6 1854.35
  4829.5 1846.96  4835.6 1845.37  4843.5 1837.63  4851.5 1837.04  4852.0 1836.54
  4861.6 1837.04  4879.7 1840.09  4915.9 1840.22  4983.6 1837.79  5007.8 1837.51
  5031.6 1841.63  5079.1 1842.76  5214.2 1840.17  5307.2 1848.11  5320.1 1852.07
  5338.5 1851.72  5383.1 1869.50  5396.9 1880.77  5420.1 1883.76  5459.0 1886.08
#Mann=7,-1,0
  4535.1    0.07       0  4539.1     0.1       0  4851.5    0.05       0
  4861.6     0.1       0  4915.9    0.07       0  4983.6     0.1       0
  5420.1    0.07       0
Bank Sta=4851.5,4861.6
Exp/Cntr=0.3,0.1

Type RM Length L Ch R = 1,15652,415,415,415
BEGIN DESCRIPTION:
Kelley Creek 32.0
END DESCRIPTION:
XS GIS Cut Line= 3
      1875025.00     13924775.00      1875425.00     13925175.00
      1875525.01     13925225.00
#Sta/Elev= 30
  4438.9 1858.96  4442.4 1858.96  4453.0 1854.62  4467.2 1852.00  4474.3 1849.83
  4509.6 1847.66  4804.4 1844.00  4891.5 1842.45  4919.7 1839.18  4948.0 1838.40
  4962.2 1837.13  4976.3 1835.16  4996.0 1835.11  4996.5 1834.61  5005.7 1834.61
  5006.2 1835.11  5013.0 1835.93  5018.6 1835.15  5035.3 1837.06  5040.9 1836.12
  5049.3 1839.60  5063.3 1849.41  5071.7 1854.78  5080.1 1855.99  5085.6 1855.46
  5094.0 1856.90  5102.4 1857.62  5108.0 1857.31  5113.6 1858.49  5116.4 1858.49
#Mann=4,-1,0
  4438.9    0.07       0  4804.4     0.1       0  4996.0    0.05       0
  5006.2     0.1       0
Bank Sta=4996,5006.2
Exp/Cntr=0.3,0.1

Type RM Length L Ch R = 1,15237,456,456,456
BEGIN DESCRIPTION:
Kelley Creek 31.0
END DESCRIPTION:
XS GIS Cut Line= 3
      1874975.05     13925424.99      1875175.00     13925375.00
      1875574.98     13925325.00
#Sta/Elev= 30
  4794.3 1911.12  4796.8 1911.12  4804.6 1909.60  4812.3 1907.30  4817.4 1907.17
  4845.8 1898.40  4853.5 1873.47  4858.7 1843.17  4866.4 1836.32  4887.0 1836.85
  4928.3 1835.42  4992.7 1834.74  4993.2 1834.24  5002.4 1834.24  5002.9 1834.74
  5038.2 1838.32  5043.2 1839.50  5060.9 1840.03  5081.0 1841.39  5101.2 1842.26
  5118.8 1842.68  5131.4 1843.55  5161.7 1844.16  5211.7 1846.27  5292.7 1849.29
  5312.8 1850.84  5344.8 1854.25  5383.4 1857.94  5401.0 1860.28  5403.5 1860.28
#Mann=5,-1,0
  4794.3     0.1       0  4992.7    0.05       0  5002.9     0.1       0
  5211.7    0.07       0  5344.8     0.1       0
Bank Sta=4992.7,5002.9
Exp/Cntr=0.3,0.1

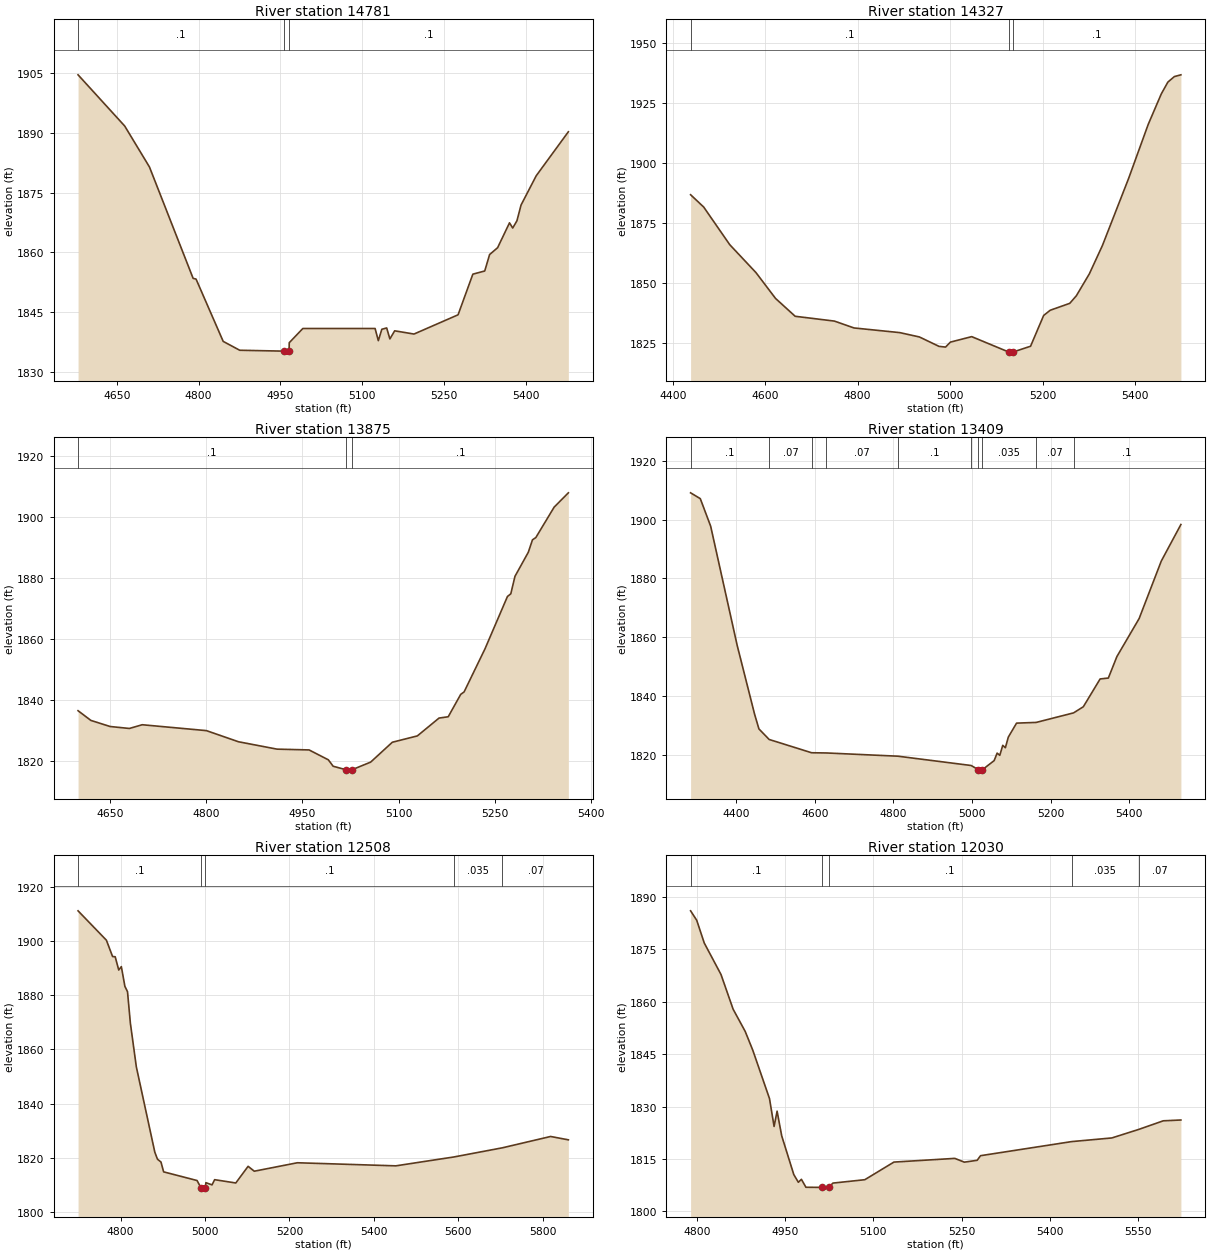
Type RM Length L Ch R = 1,14781,454,454,454
BEGIN DESCRIPTION:
Kelley Creek 30.0
END DESCRIPTION:
XS GIS Cut Line= 3
      1874974.98     13925574.99      1875375.00     13925725.00
      1875774.98     13925475.01
#Sta/Elev= 30
  4579.0 1904.48  4664.5 1891.66  4709.9 1881.40  4790.0 1853.48  4795.3 1853.32
  4845.1 1837.70  4875.4 1835.48  4955.7 1835.26  4956.2 1834.76  4965.9 1835.26
  4966.2 1837.37  4991.1 1840.93  5123.6 1840.93  5129.5 1837.88  5135.9 1840.73
  5144.8 1841.07  5150.7 1838.32  5159.5 1840.35  5194.9 1839.54  5275.7 1844.36
  5302.8 1854.54  5324.6 1855.34  5333.5 1859.45  5348.2 1861.17  5370.0 1867.40
  5375.9 1866.10  5383.6 1867.91  5391.2 1871.87  5419.0 1879.20  5477.9 1890.21
#Mann=3,-1,0
  4579.0     0.1       0  4955.7    0.05       0  4965.9     0.1       0
Bank Sta=4955.7,4965.9
Exp/Cntr=0.3,0.1

Type RM Length L Ch R = 1,14327,452,452,452
BEGIN DESCRIPTION:
Kelley Creek 29.0
END DESCRIPTION:
XS GIS Cut Line= 3
      1875025.02     13925725.02      1875425.00     13926125.00
      1875774.98     13926474.98
#Sta/Elev= 30
  4438.7 1886.77  4467.0 1881.63  4523.5 1865.87  4580.1 1854.23  4622.5 1843.42
  4664.9 1835.97  4749.8 1833.96  4792.2 1831.09  4891.2 1829.14  4933.6 1827.33
  4976.1 1823.39  4990.2 1823.10  5000.8 1825.18  5046.8 1827.46  5126.4 1821.07
  5126.9 1820.57  5136.9 1821.07  5174.1 1823.45  5202.4 1836.30  5216.5 1838.48
  5258.9 1841.38  5273.1 1844.53  5301.3 1853.71  5329.6 1865.57  5386.2 1893.57
  5428.6 1916.16  5456.9 1928.91  5471.1 1933.83  5485.2 1936.15  5499.3 1936.88
#Mann=3,-1,0
  4438.7     0.1       0  5126.4    0.05       0  5136.9     0.1       0
Bank Sta=5126.4,5136.9
Exp/Cntr=0.3,0.1

Type RM Length L Ch R = 1,13875,466,466,466
BEGIN DESCRIPTION:
Kelley Creek 28.0
END DESCRIPTION:
XS GIS Cut Line= 3
      1875075.00     13925974.97      1875075.00     13926375.00
      1875174.99     13926724.97
#Sta/Elev= 30
  4600.3 1836.43  4620.3 1833.25  4650.3 1831.25  4680.3 1830.61  4700.3 1831.83
  4800.3 1829.90  4850.3 1826.25  4910.3 1823.83  4960.3 1823.57  4990.3 1820.33
  4997.8 1818.22  5017.1 1817.12  5017.6 1816.62  5027.7 1817.12  5056.2 1819.57
  5090.0 1826.09  5129.0 1828.17  5162.8 1834.02  5177.1 1834.45  5196.6 1841.80
  5201.8 1842.58  5234.3 1856.68  5269.4 1873.89  5274.6 1874.76  5281.1 1880.49
  5301.9 1888.40  5308.4 1892.47  5313.6 1893.21  5342.2 1903.20  5364.3 1907.88
#Mann=3,-1,0
  4600.3     0.1       0  5017.1    0.05       0  5027.7     0.1       0
Bank Sta=5017.1,5027.7
Exp/Cntr=0.3,0.1

Type RM Length L Ch R = 1,13409,901,901,901
BEGIN DESCRIPTION:
Kelley Creek 27.0
END DESCRIPTION:
XS GIS Cut Line= 3
      1874774.99     13925725.04      1874625.00     13926425.00
      1874975.03     13926825.03
#Sta/Elev= 30
  4284.1 1909.09  4308.8 1907.11  4335.2 1897.74  4402.5 1857.35  4446.8 1833.97
  4457.9 1828.92  4484.0 1825.33  4592.0 1820.82  4629.5 1820.75  4811.6 1819.65
  4997.9 1816.49  5016.0 1815.08  5016.5 1814.58  5026.7 1815.08  5056.4 1818.15
  5064.0 1820.70  5070.7 1819.94  5078.3 1823.34  5084.9 1822.52  5092.5 1826.15
  5113.4 1830.88  5163.3 1831.12  5258.5 1834.36  5283.3 1836.45  5326.0 1845.88
  5346.9 1846.19  5368.7 1853.49  5425.2 1866.38  5481.6 1885.92  5531.5 1898.33
#Mann=10,-1,0
  4284.1     0.1       0  4484.0    0.07       0  4592.0     0.1       0
  4629.5    0.07       0  4811.6     0.1       0  4997.9   0.035       0
  5016.0   0.035       0  5026.7   0.035       0  5163.3    0.07       0
  5258.5     0.1       0
Bank Sta=5016,5026.7
Exp/Cntr=0.3,0.1

Type RM Length L Ch R = 1,12508,478,478,478
BEGIN DESCRIPTION:
Kelley Creek 26.1
END DESCRIPTION:
XS GIS Cut Line= 5
      1874664.52     13925650.36      1874258.26     13925952.46
      1874187.95     13926134.75      1874213.99     13926254.54
      1874379.27     13926548.98
#Sta/Elev= 30
  4699.2 1911.18  4766.4 1900.32  4781.0 1894.30  4787.2 1894.21  4795.6 1889.32
  4801.8 1890.57  4810.2 1883.28  4816.4 1881.30  4823.2 1869.67  4837.3 1853.55
  4881.1 1822.02  4887.4 1819.43  4895.7 1818.38  4902.0 1814.75  4981.2 1811.55
  4990.5 1808.87  4991.0 1808.37  5001.2 1808.87  5002.1 1810.75  5016.7 1809.94
  5022.9 1811.86  5073.0 1810.64  5102.2 1816.80  5116.8 1814.99  5218.9 1818.11
  5452.3 1816.97  5589.8 1820.25  5704.7 1823.63  5819.1 1827.82  5861.1 1826.58
#Mann=5,-1,0
  4699.2     0.1       0  4990.5    0.05       0  5001.2     0.1       0
  5589.8   0.035       0  5704.7    0.07       0
Bank Sta=4990.5,5001.2
Exp/Cntr=0.3,0.1

Type RM Length L Ch R = 1,12030,455,455,455
BEGIN DESCRIPTION:
Kelley Creek 26.0
END DESCRIPTION:
XS GIS Cut Line= 3
      1874075.01     13925724.96      1874025.00     13925925.00
      1874325.00     13926475.00
#Sta/Elev= 30
  4789.5 1886.08  4799.9 1883.38  4812.7 1876.86  4841.1 1867.85  4861.7 1857.90
  4882.3 1851.50  4895.2 1846.10  4923.5 1832.27  4931.3 1824.28  4936.4 1828.66
  4944.2 1821.62  4964.8 1810.48  4972.5 1808.29  4977.7 1809.13  4985.4 1806.85
  5013.1 1806.82  5013.6 1806.32  5023.9 1806.82  5031.3 1808.05  5085.4 1809.02
  5134.8 1814.07  5238.2 1815.13  5254.4 1814.05  5276.2 1814.58  5281.9 1815.90
  5436.6 1819.94  5505.0 1820.99  5550.7 1823.44  5592.3 1825.90  5622.2 1826.13
#Mann=5,-1,0
  4789.5     0.1       0  5013.1    0.05       0  5023.9     0.1       0
  5436.6   0.035       0  5550.7    0.07       0
Bank Sta=5013.1,5023.9
Exp/Cntr=0.3,0.1

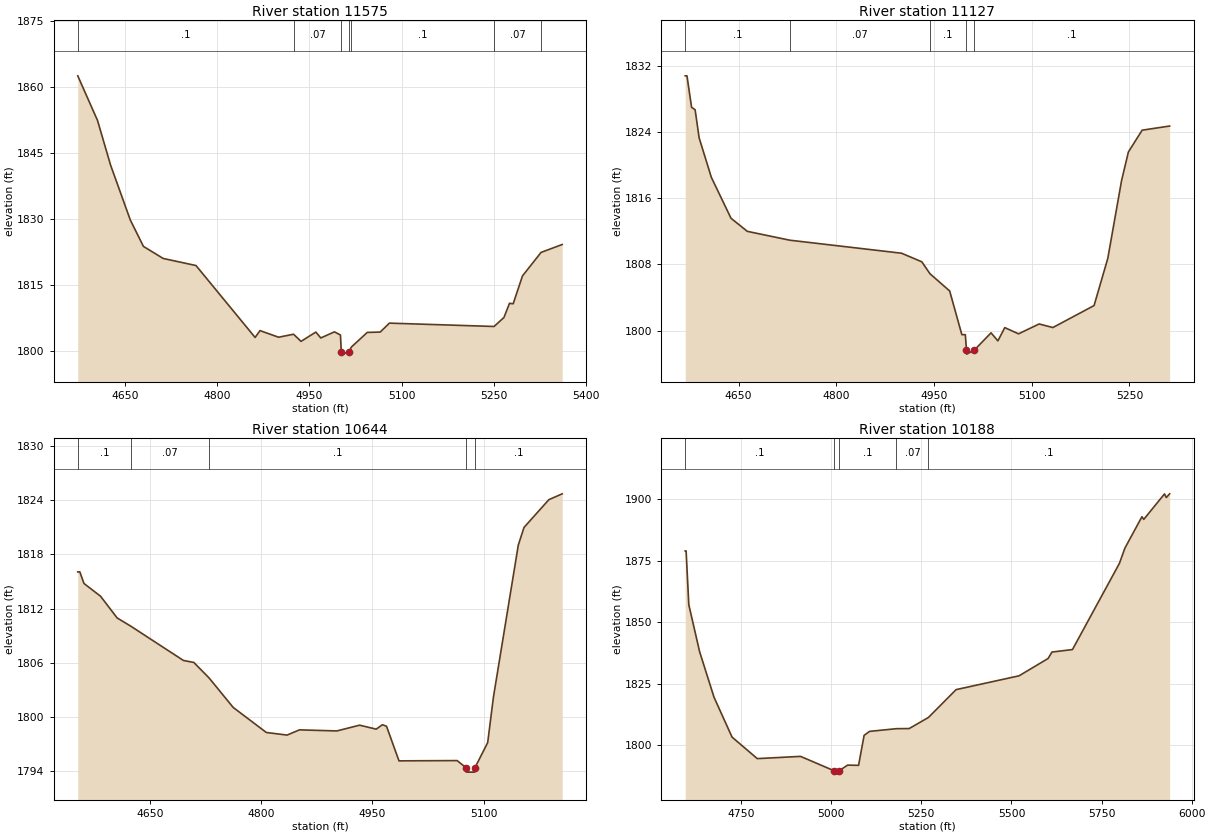
Type RM Length L Ch R = 1,11575,448,448,448
BEGIN DESCRIPTION:
Kelley Creek 25.0
END DESCRIPTION:
XS GIS Cut Line= 3
      1873474.99     13926175.00      1873875.00     13926325.00
      1874175.03     13926525.02
#Sta/Elev= 30
  4573.2 1862.52  4605.3 1852.40  4626.6 1842.24  4658.7 1829.76  4680.0 1823.78
  4712.1 1821.04  4765.5 1819.43  4861.6 1803.10  4869.6 1804.65  4899.8 1803.15
  4924.1 1803.83  4936.3 1802.21  4960.4 1804.32  4968.4 1802.98  4990.6 1804.37
  5000.4 1803.65  5001.8 1799.81  5002.3 1799.31  5014.0 1799.81  5018.3 1800.94
  5044.0 1804.24  5065.0 1804.32  5080.0 1806.35  5250.2 1805.59  5266.3 1807.64
  5275.3 1810.85  5281.3 1810.75  5296.4 1817.07  5326.6 1822.41  5361.0 1824.21
#Mann=7,-1,0
  4573.2     0.1       0  4924.1    0.07       0  5001.8    0.05       0
  5014.0    0.07       0  5018.3     0.1       0  5250.2    0.07       0
  5326.6     0.1       0
Bank Sta=5001.8,5014
Exp/Cntr=0.3,0.1

Type RM Length L Ch R = 1,11127,483,483,483
BEGIN DESCRIPTION:
Kelley Creek 24.0
END DESCRIPTION:
XS GIS Cut Line= 3
      1873524.97     13926875.01      1873925.00     13926725.00
      1874225.04     13926624.99
#Sta/Elev= 30
  4568.2 1830.77  4570.9 1830.77  4578.0 1826.97  4583.4 1826.68  4589.6 1823.28
  4608.3 1818.52  4638.5 1813.58  4663.5 1812.00  4728.8 1810.93  4900.2 1809.36
  4931.4 1808.32  4943.8 1806.89  4974.1 1804.80  4992.8 1799.53  4998.1 1799.53
  4999.9 1797.68  5000.4 1797.18  5012.1 1797.68  5037.6 1799.75  5048.1 1798.78
  5058.7 1800.38  5079.8 1799.63  5111.4 1800.82  5132.5 1800.39  5195.7 1803.04
  5216.8 1808.74  5237.9 1818.12  5248.4 1821.58  5269.5 1824.21  5311.7 1824.71
#Mann=5,-1,0
  4568.2     0.1       0  4728.8    0.07       0  4943.8     0.1       0
  4999.9    0.05       0  5012.1     0.1       0
Bank Sta=4999.9,5012.1
Exp/Cntr=0.3,0.1

Type RM Length L Ch R = 1,10644,456,456,456
BEGIN DESCRIPTION:
Kelley Creek 23.0
END DESCRIPTION:
XS GIS Cut Line= 3
      1873625.03     13926975.02      1874025.00     13927175.00
      1874224.97     13927224.99
#Sta/Elev= 30
  4552.8 1816.07  4555.6 1816.07  4561.2 1814.78  4583.5 1813.37  4605.9 1810.96
  4624.6 1810.03  4695.3 1806.24  4709.3 1806.02  4729.9 1804.30  4762.4 1801.03
  4807.1 1798.25  4835.1 1797.96  4851.8 1798.54  4902.2 1798.42  4932.9 1799.06
  4955.3 1798.62  4963.6 1799.11  4969.2 1798.94  4986.0 1795.10  5064.4 1795.13
  5076.3 1794.35  5076.8 1793.85  5088.0 1793.85  5088.5 1794.35  5105.6 1797.12
  5113.4 1802.19  5146.9 1819.04  5154.6 1821.00  5188.1 1824.08  5206.1 1824.73
#Mann=5,-1,0
  4552.8     0.1       0  4624.6    0.07       0  4729.9     0.1       0
  5076.3    0.05       0  5088.5     0.1       0
Bank Sta=5076.3,5088.5
Exp/Cntr=0.3,0.1

Type RM Length L Ch R = 1,10188,369,369,369
BEGIN DESCRIPTION:
Kelley Creek 22.0
END DESCRIPTION:
XS GIS Cut Line= 3
      1873474.98     13927575.00      1873875.00     13927575.00
      1874807.62     13927428.32
#Sta/Elev= 30
  4594.8 1878.91  4597.3 1878.91  4604.8 1857.03  4634.8 1837.93  4674.8 1819.42
  4724.8 1803.23  4794.8 1794.49  4914.8 1795.40  5008.9 1789.50  5009.4 1789.00
  5021.2 1789.50  5045.4 1791.84  5075.8 1791.76  5091.2 1803.94  5106.2 1805.56
  5181.0 1806.66  5216.3 1806.71  5269.8 1811.23  5346.4 1822.53  5521.2 1828.15
  5601.7 1835.19  5612.3 1837.80  5669.3 1838.82  5799.5 1873.83  5814.8 1880.04
  5862.0 1892.80  5867.1 1891.72  5924.6 1902.08  5929.6 1900.61  5938.9 1902.11
#Mann=5,-1,0
  4594.8     0.1       0  5008.9    0.05       0  5021.2     0.1       0
  5181.0    0.07       0  5269.8     0.1       0
Bank Sta=5008.9,5021.2
Exp/Cntr=0.3,0.1