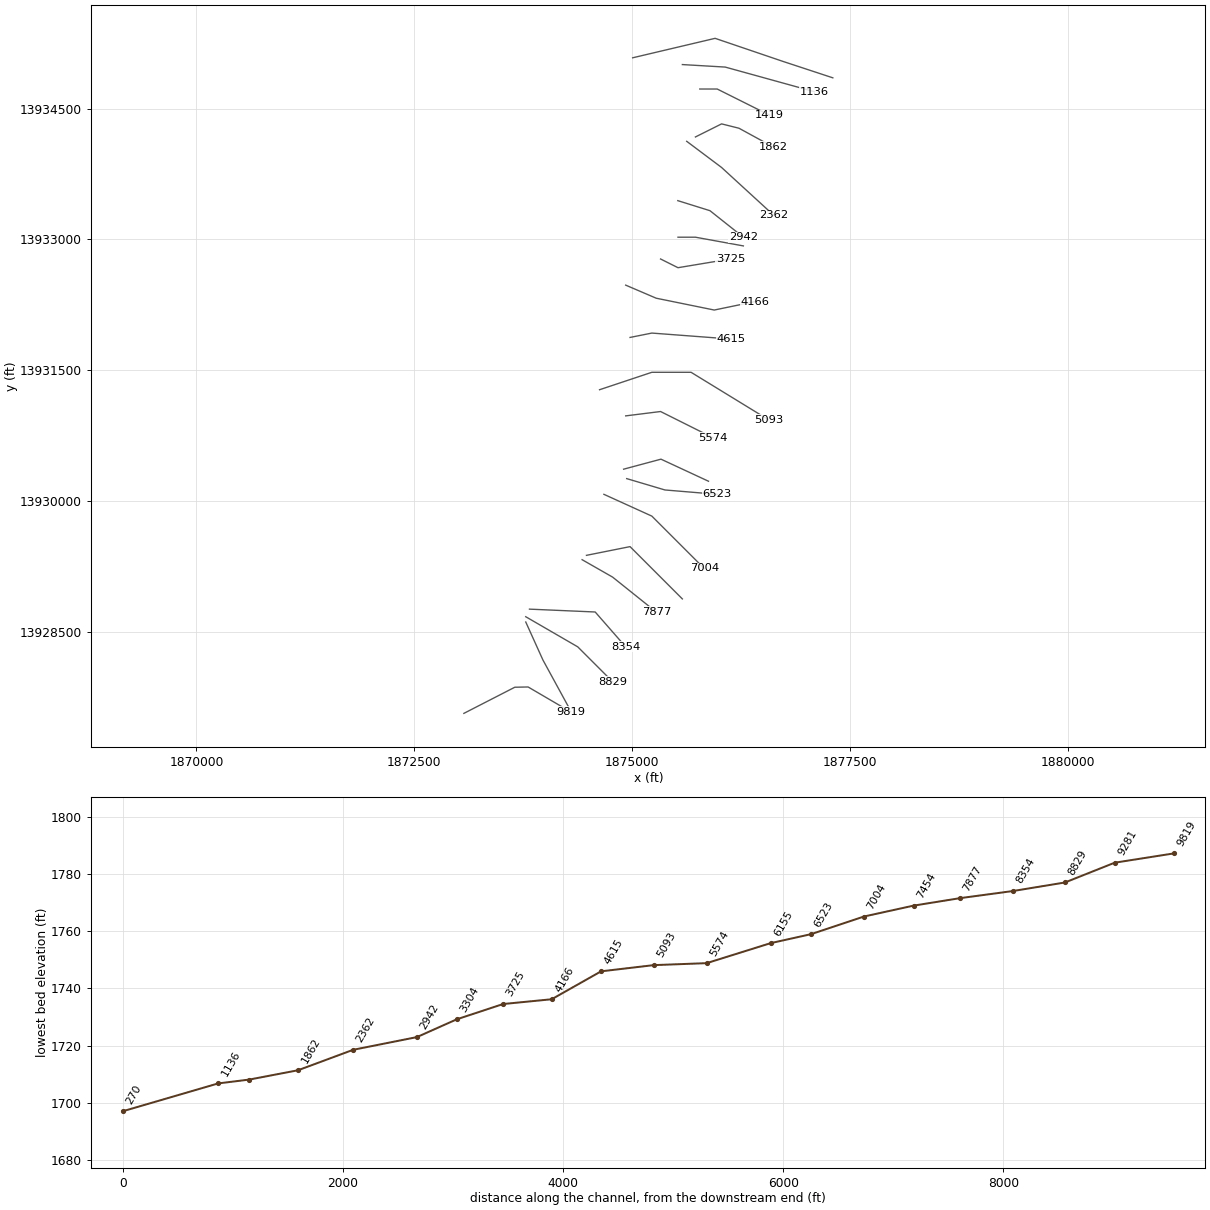
HEC-RAS study Kelley Creek.prj: Kelley Creek Base Level Engineering

--- Kelley Creek.g01 (geometry) --- (continued)

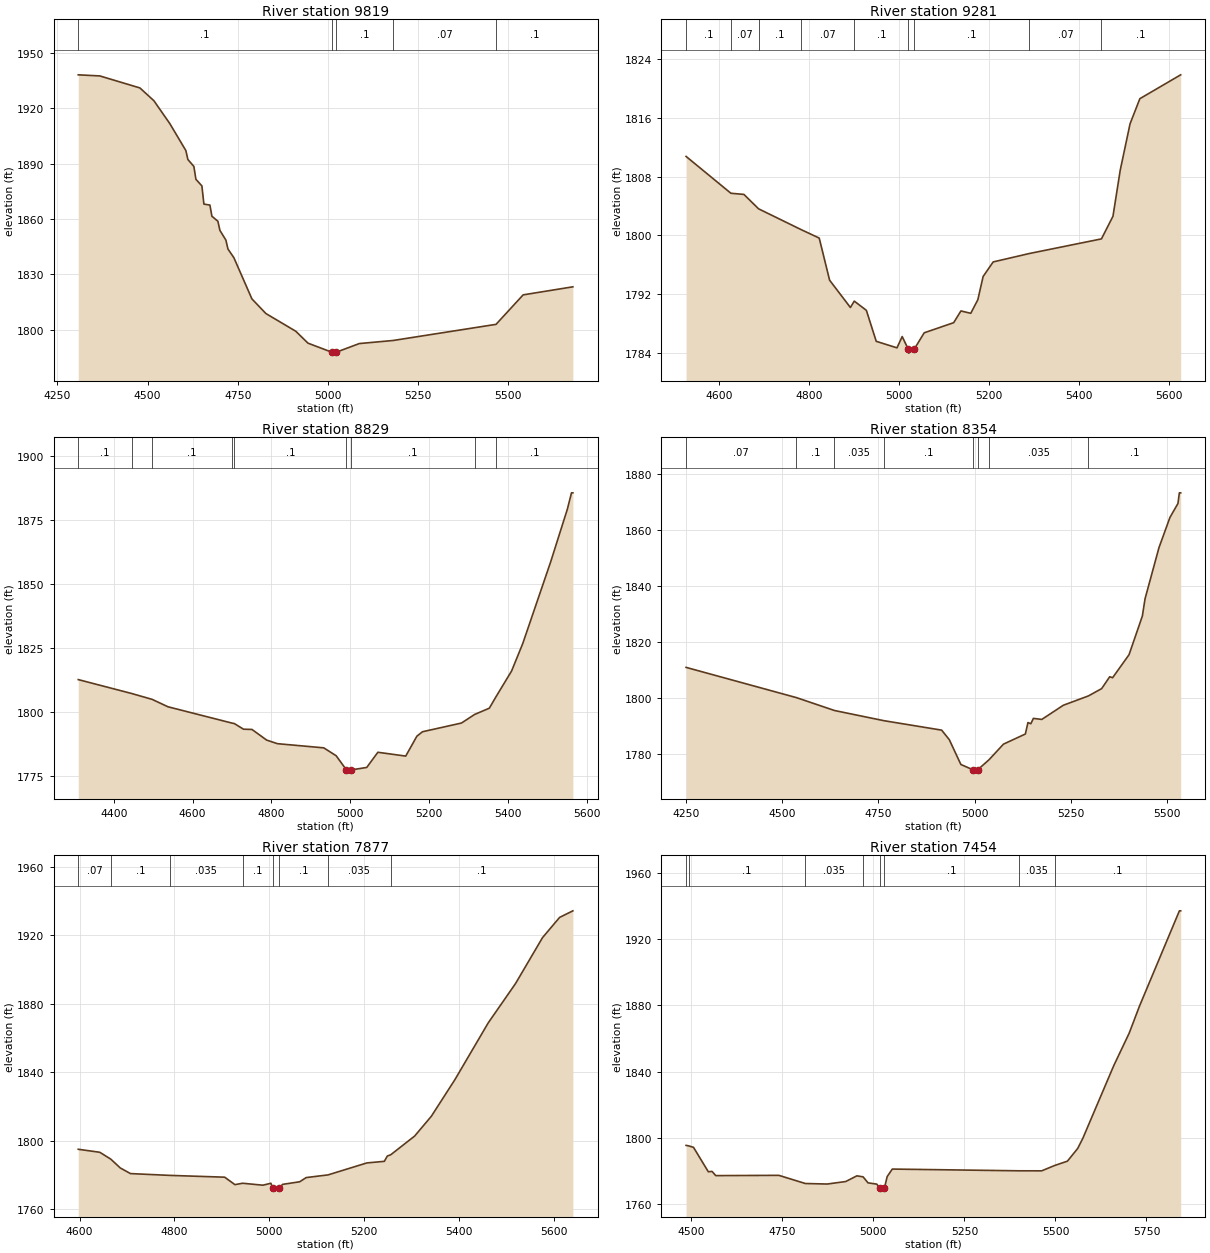
Type RM Length L Ch R = 1,9819,538,538,538
BEGIN DESCRIPTION:
Kelley Creek 21.0
END DESCRIPTION:
XS GIS Cut Line= 4
      1873068.44     13927561.81      1873652.63     13927861.68
      1873805.44     13927864.67      1874290.38     13927581.23
#Sta/Elev= 30
  4307.8 1938.15  4367.6 1937.55  4478.6 1931.05  4517.4 1924.12  4561.7 1911.67
  4606.1 1897.06  4611.7 1892.21  4628.3 1888.46  4633.9 1881.50  4650.5 1877.91
  4656.1 1868.03  4672.7 1867.51  4678.3 1861.46  4694.9 1858.71  4700.5 1853.77
  4717.1 1848.51  4722.7 1843.70  4739.2 1838.96  4789.2 1816.62  4828.0 1808.67
  4910.9 1799.06  4944.6 1792.61  5010.7 1787.70  5011.2 1787.20  5023.0 1787.70
  5086.9 1792.39  5180.8 1794.06  5466.0 1802.81  5541.1 1818.80  5679.0 1823.17
#Mann=5,-1,0
  4307.8     0.1       0  5010.7    0.05       0  5023.0     0.1       0
  5180.8    0.07       0  5466.0     0.1       0
Bank Sta=5010.7,5023
Exp/Cntr=0.3,0.1

Type RM Length L Ch R = 1,9281,452,452,452
BEGIN DESCRIPTION:
Kelley Creek 20.0
END DESCRIPTION:
XS GIS Cut Line= 3
      1873778.39     13928610.13      1873975.00     13928175.00
      1874272.83     13927629.26
#Sta/Elev= 30
  4526.7 1810.76  4626.3 1805.74  4655.3 1805.58  4687.8 1803.62  4781.2 1800.82
  4822.6 1799.63  4845.7 1793.89  4891.9 1790.17  4900.5 1791.04  4927.4 1789.78
  4949.3 1785.56  4995.4 1784.67  5007.0 1786.21  5020.7 1784.45  5021.2 1783.95
  5033.3 1784.45  5055.9 1786.72  5121.4 1788.10  5137.5 1789.70  5159.4 1789.38
  5175.1 1791.23  5186.9 1794.40  5209.2 1796.38  5289.9 1797.53  5449.8 1799.52
  5475.4 1802.60  5491.6 1808.90  5513.4 1815.21  5535.2 1818.63  5625.9 1821.88
#Mann=9,-1,0
  4526.7     0.1       0  4626.3    0.07       0  4687.8     0.1       0
  4781.2    0.07       0  4900.5     0.1       0  5020.7    0.05       0
  5033.3     0.1       0  5289.9    0.07       0  5449.8     0.1       0
Bank Sta=5020.7,5033.3
Exp/Cntr=0.3,0.1

Type RM Length L Ch R = 1,8829,475,475,475
BEGIN DESCRIPTION:
Kelley Creek 19.0
END DESCRIPTION:
XS GIS Cut Line= 3
      1873778.10     13928670.77      1874375.00     13928325.00
      1874774.99     13927925.01
#Sta/Elev= 30
  4309.9 1812.70  4445.6 1807.27  4497.3 1805.00  4537.5 1802.11  4701.1 1795.71
  4706.0 1795.57  4729.3 1793.37  4750.8 1793.27  4788.1 1789.13  4815.4 1787.73
  4933.0 1786.10  4964.5 1783.03  4990.5 1777.53  4991.0 1777.03  5003.2 1777.53
  5042.1 1778.46  5070.4 1784.38  5141.1 1782.89  5169.4 1790.64  5183.6 1792.37
  5282.6 1795.77  5315.9 1799.11  5353.3 1801.55  5369.6 1805.85  5409.8 1816.05
  5438.1 1826.72  5508.8 1858.48  5551.3 1879.07  5561.9 1885.48  5565.4 1885.48
#Mann=9,-1,0
  4309.9     0.1       0  4445.6    0.07       0  4497.3     0.1       0
  4701.1   0.035       0  4706.0     0.1       0  4990.5    0.05       0
  5003.2     0.1       0  5315.9    0.07       0  5369.6     0.1       0
Bank Sta=4990.5,5003.2
Exp/Cntr=0.3,0.1

Type RM Length L Ch R = 1,8354,477,477,477
BEGIN DESCRIPTION:
Kelley Creek 18.0
END DESCRIPTION:
XS GIS Cut Line= 3
      1873821.04     13928757.68      1874575.00     13928725.00
      1874925.02     13928324.98
#Sta/Elev= 30
  4249.9 1811.03  4537.0 1800.24  4635.8 1795.65  4764.3 1792.02  4914.5 1788.65
  4934.5 1785.23  4964.5 1776.40  4995.7 1774.53  4996.2 1774.03  5008.4 1774.53
  5037.5 1778.06  5075.3 1783.66  5132.2 1787.27  5138.9 1791.34  5146.5 1790.95
  5153.1 1792.84  5174.9 1792.47  5230.9 1797.52  5296.3 1800.86  5330.6 1803.46
  5351.5 1807.68  5359.1 1807.35  5401.8 1815.55  5436.4 1829.32  5443.5 1835.54
  5479.6 1853.71  5508.1 1864.49  5529.0 1869.49  5532.7 1873.28  5536.1 1873.28
#Mann=8,-1,0
  4249.9    0.07       0  4537.0     0.1       0  4635.8   0.035       0
  4764.3     0.1       0  4995.7    0.05       0  5008.4     0.1       0
  5037.5   0.035       0  5296.3     0.1       0
Bank Sta=4995.7,5008.4
Exp/Cntr=0.3,0.1

Type RM Length L Ch R = 1,7877,423,423,423
BEGIN DESCRIPTION:
Kelley Creek 17.0
END DESCRIPTION:
XS GIS Cut Line= 3
      1874424.96     13929325.02      1874775.00     13929125.00
      1875275.03     13928724.98
#Sta/Elev= 30
  4597.1 1794.88  4642.5 1793.12  4665.8 1789.09  4685.7 1783.95  4707.3 1780.65
  4790.1 1779.60  4906.0 1778.55  4927.6 1774.19  4943.9 1775.00  4986.6 1773.86
  5003.5 1774.99  5007.4 1772.06  5007.9 1771.56  5020.4 1772.06  5028.3 1774.35
  5064.3 1775.86  5077.9 1778.32  5124.1 1779.89  5206.0 1786.89  5242.8 1787.82
  5249.2 1790.94  5256.2 1791.64  5306.8 1802.62  5342.0 1814.19  5391.6 1835.57
  5462.1 1868.86  5519.7 1891.87  5576.5 1918.68  5612.6 1930.53  5640.6 1934.38
#Mann=8,-1,0
  4597.1    0.07       0  4665.8     0.1       0  4790.1   0.035       0
  4943.9     0.1       0  5007.4    0.05       0  5020.4     0.1       0
  5124.1   0.035       0  5256.2     0.1       0
Bank Sta=5007.4,5020.4
Exp/Cntr=0.3,0.1

Type RM Length L Ch R = 1,7454,450,450,450
BEGIN DESCRIPTION:
Kelley Creek 16.0
END DESCRIPTION:
XS GIS Cut Line= 3
      1874475.04     13929375.01      1874975.00     13929475.00
      1875575.01     13928874.99
#Sta/Elev= 30
  4485.5 1795.39  4492.5 1795.10  4505.9 1794.22  4546.6 1779.45  4556.8 1779.65
  4567.0 1777.12  4740.4 1777.27  4813.0 1772.34  4873.0 1772.02  4924.0 1773.54
  4954.6 1776.97  4971.6 1776.38  4985.2 1772.74  5009.5 1771.95  5017.1 1769.44
  5017.6 1768.94  5030.1 1769.44  5037.8 1776.51  5051.9 1781.07  5399.6 1780.02
  5462.1 1780.00  5497.4 1783.20  5532.8 1785.85  5561.0 1793.52  5575.2 1799.69
  5660.0 1843.59  5702.5 1863.29  5730.8 1879.65  5840.4 1937.25  5843.9 1937.25
#Mann=8,-1,0
  4485.5    0.07       0  4492.5     0.1       0  4813.0   0.035       0
  4971.6     0.1       0  5017.1    0.05       0  5030.1     0.1       0
  5399.6   0.035       0  5497.4     0.1       0
Bank Sta=5017.1,5030.1
Exp/Cntr=0.3,0.1

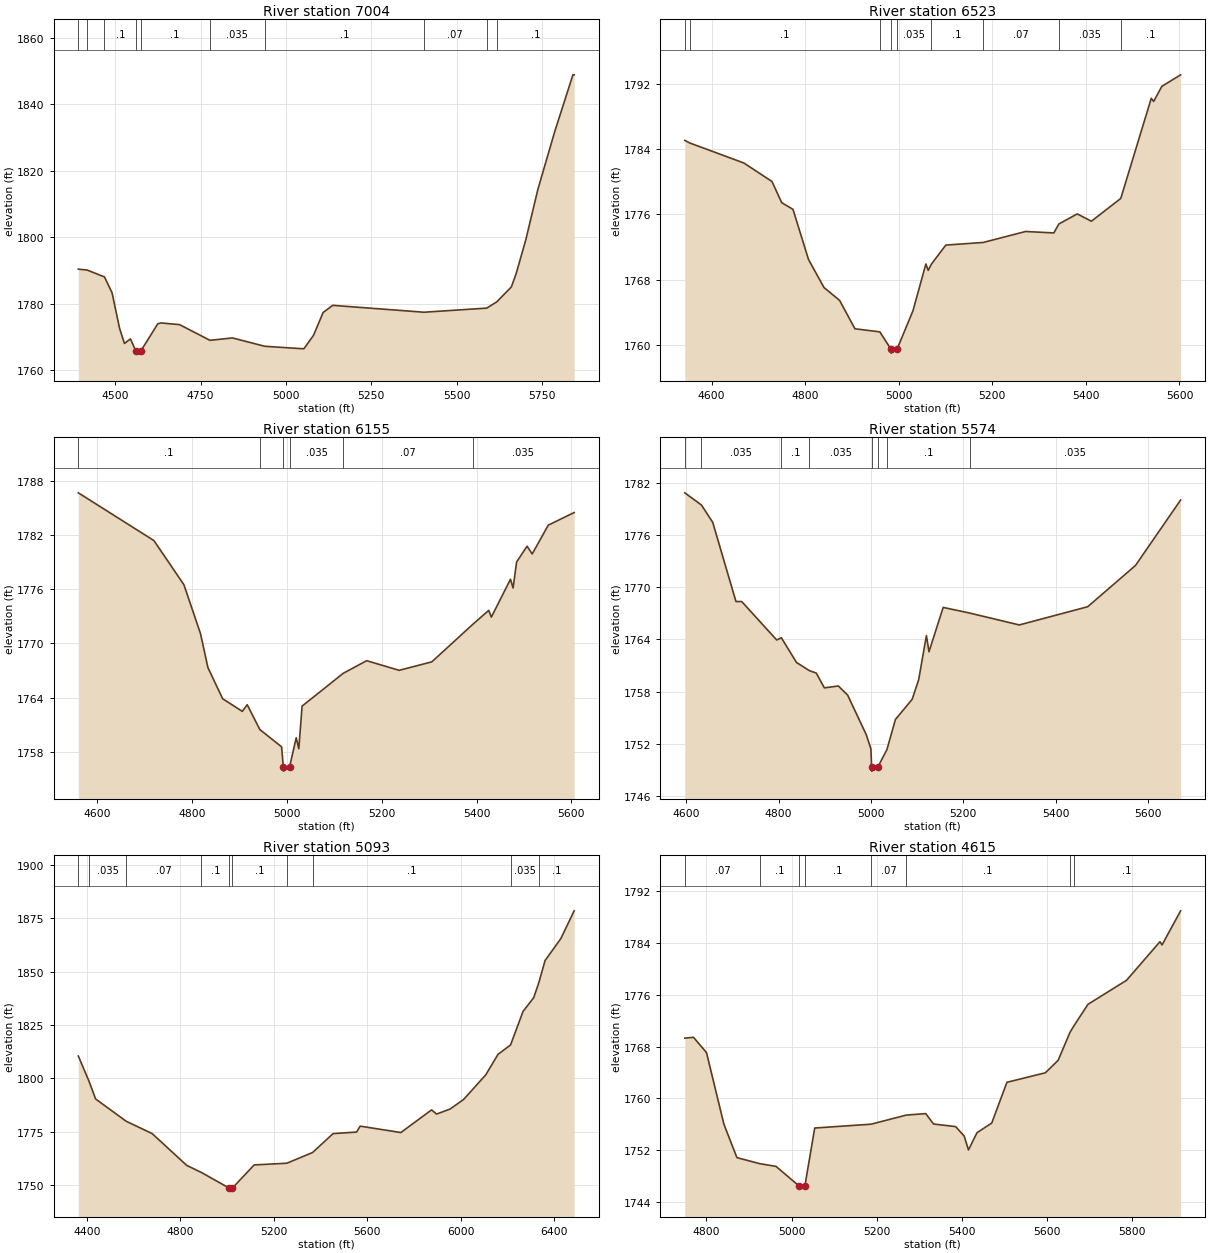
Type RM Length L Ch R = 1,7004,481,481,481
BEGIN DESCRIPTION:
Kelley Creek 15.0
END DESCRIPTION:
XS GIS Cut Line= 3
      1874675.02     13930074.99      1875225.00     13929825.00
      1875825.03     13929224.97
#Sta/Elev= 30
  4391.6 1790.40  4417.2 1790.13  4468.2 1788.06  4490.4 1783.30  4512.4 1772.60
  4526.7 1768.04  4544.3 1769.42  4560.8 1765.64  4561.3 1765.14  4573.8 1765.64
  4624.4 1773.95  4633.2 1774.22  4688.2 1773.71  4777.3 1768.99  4843.0 1769.71
  4937.9 1767.20  5052.3 1766.44  5080.6 1770.48  5108.9 1777.37  5137.1 1779.51
  5404.1 1777.44  5587.9 1778.67  5617.4 1780.54  5660.4 1785.06  5674.6 1789.12
  5702.8 1799.30  5738.2 1814.46  5787.7 1831.87  5840.7 1848.83  5844.3 1848.83
#Mann=10,-1,0
  4391.6     0.1       0  4417.2    0.07       0  4468.2     0.1       0
  4560.8    0.05       0  4573.8     0.1       0  4777.3   0.035       0
  4937.9     0.1       0  5404.1    0.07       0  5587.9   0.035       0
  5617.4     0.1       0
Bank Sta=4560.8,4573.8
Exp/Cntr=0.3,0.1

Type RM Length L Ch R = 1,6523,368,368,368
BEGIN DESCRIPTION:
Kelley Creek 14.0
END DESCRIPTION:
XS GIS Cut Line= 3
      1874936.43     13930255.23      1875375.00     13930125.00
      1875975.02     13930075.00
#Sta/Elev= 30
  4542.9 1785.10  4553.5 1784.78  4669.2 1782.32  4729.2 1780.05  4750.0 1777.45
  4774.1 1776.63  4807.3 1770.47  4840.5 1767.02  4873.7 1765.45  4906.5 1761.96
  4959.7 1761.58  4983.3 1759.47  4983.8 1758.97  4996.6 1759.47  5030.5 1764.17
  5058.1 1769.92  5063.1 1769.13  5069.4 1769.86  5100.7 1772.24  5180.5 1772.56
  5271.3 1773.91  5331.5 1773.73  5342.2 1774.83  5381.7 1776.07  5411.8 1775.17
  5474.6 1777.97  5539.8 1790.27  5544.8 1789.88  5562.3 1791.73  5602.5 1793.15
#Mann=9,-1,0
  4542.9    0.07       0  4553.5     0.1       0  4959.7   0.035       0
  4983.3   0.035       0  4996.6   0.035       0  5069.4     0.1       0
  5180.5    0.07       0  5342.2   0.035       0  5474.6     0.1       0
Bank Sta=4983.3,4996.6
Exp/Cntr=0.3,0.1

Type RM Length L Ch R = 1,6155,581,581,581
BEGIN DESCRIPTION:
Kelley Creek 13.0
END DESCRIPTION:
XS GIS Cut Line= 3
      1874901.21     13930363.42      1875329.77     13930478.29
      1875875.02     13930224.99
#Sta/Elev= 30
  4560.9 1786.74  4720.1 1781.44  4783.4 1776.53  4818.3 1771.11  4834.0 1767.32
  4865.1 1763.86  4906.5 1762.46  4916.8 1763.20  4943.4 1760.44  4989.3 1758.52
  4992.8 1756.32  4993.3 1755.82  5006.2 1756.32  5020.1 1759.53  5025.6 1758.31
  5032.4 1763.04  5119.2 1766.69  5168.5 1768.09  5237.1 1767.02  5305.8 1767.96
  5392.0 1772.12  5425.8 1773.68  5431.3 1772.93  5471.6 1777.14  5477.1 1776.17
  5484.5 1779.05  5506.5 1780.81  5517.4 1779.95  5551.3 1783.15  5605.8 1784.55
#Mann=6,-1,0
  4560.9     0.1       0  4943.4   0.035       0  4992.8   0.035       0
  5006.2   0.035       0  5119.2    0.07       0  5392.0   0.035       0
Bank Sta=4992.8,5006.2
Exp/Cntr=0.3,0.1

Type RM Length L Ch R = 1,5574,481,481,481
BEGIN DESCRIPTION:
Kelley Creek 12.0
END DESCRIPTION:
XS GIS Cut Line= 3
      1874925.02     13930975.00      1875325.00     13931025.00
      1875924.99     13930725.01
#Sta/Elev= 30
  4596.9 1780.89  4632.9 1779.49  4657.4 1777.49  4707.7 1768.37  4720.3 1768.36
  4795.9 1763.94  4806.1 1764.19  4838.8 1761.35  4866.9 1760.40  4881.6 1760.13
  4899.2 1758.42  4929.5 1758.64  4949.6 1757.59  4989.9 1753.03  5000.0 1751.40
  5001.5 1749.33  5002.0 1748.83  5015.3 1749.33  5034.7 1751.31  5053.1 1754.78
  5089.4 1757.11  5103.4 1759.35  5120.2 1764.44  5125.8 1762.58  5156.5 1767.69
  5213.8 1767.04  5321.4 1765.67  5469.6 1767.77  5573.0 1772.52  5670.8 1780.06
#Mann=8,-1,0
  4596.9     0.1       0  4632.9   0.035       0  4806.1     0.1       0
  4866.9   0.035       0  5001.5   0.035       0  5015.3   0.035       0
  5034.7     0.1       0  5213.8   0.035       0
Bank Sta=5001.5,5015.3
Exp/Cntr=0.3,0.1

Type RM Length L Ch R = 1,5093,478,478,478
BEGIN DESCRIPTION:
Kelley Creek 11.0
END DESCRIPTION:
XS GIS Cut Line= 4
      1874625.02     13931275.01      1875225.00     13931475.00
      1875675.00     13931475.00      1876561.42     13930931.90
#Sta/Elev= 30
  4363.0 1810.47  4409.1 1798.57  4436.8 1790.39  4567.2 1779.96  4679.2 1774.13
  4826.8 1759.26  4889.9 1755.93  5008.5 1748.64  5009.0 1748.14  5022.4 1748.64
  5115.4 1759.47  5255.4 1760.27  5365.5 1765.28  5453.2 1774.14  5553.8 1774.86
  5569.2 1777.64  5743.3 1774.63  5874.8 1785.25  5896.1 1783.28  5954.1 1785.65
  6012.2 1790.17  6106.9 1801.69  6159.1 1811.25  6212.8 1815.66  6266.4 1831.39
  6311.9 1837.77  6334.2 1844.96  6360.4 1855.16  6428.0 1865.46  6485.0 1878.46
#Mann=10,-1,0
  4363.0     0.1       0  4409.1   0.035       0  4567.2    0.07       0
  4889.9     0.1       0  5008.5    0.05       0  5022.4     0.1       0
  5255.4    0.07       0  5365.5     0.1       0  6212.8   0.035       0
  6334.2     0.1       0
Bank Sta=5008.5,5022.4
Exp/Cntr=0.3,0.1

Type RM Length L Ch R = 1,4615,449,449,449
BEGIN DESCRIPTION:
Kelley Creek 10.0
END DESCRIPTION:
XS GIS Cut Line= 3
      1874974.99     13931875.00      1875225.00     13931925.00
      1876131.76     13931856.60
#Sta/Elev= 30
  4749.3 1769.32  4769.7 1769.45  4800.3 1767.08  4841.1 1756.02  4871.7 1750.84
  4925.8 1749.90  4963.5 1749.49  5017.4 1746.47  5017.9 1745.97  5031.3 1746.47
  5054.4 1755.42  5186.5 1756.01  5269.4 1757.42  5315.1 1757.65  5333.4 1756.04
  5385.3 1755.64  5405.4 1754.17  5415.4 1752.03  5435.5 1754.70  5470.1 1756.19
  5505.7 1762.49  5595.9 1763.96  5626.0 1765.89  5653.9 1770.23  5662.6 1771.18
  5696.2 1774.56  5786.5 1778.26  5865.0 1784.23  5870.0 1783.74  5913.6 1789.01
#Mann=8,-1,0
  4749.3    0.07       0  4925.8     0.1       0  5017.4    0.05       0
  5031.3     0.1       0  5186.5    0.07       0  5269.4     0.1       0
  5653.9    0.07       0  5662.6     0.1       0
Bank Sta=5017.4,5031.3
Exp/Cntr=0.3,0.1

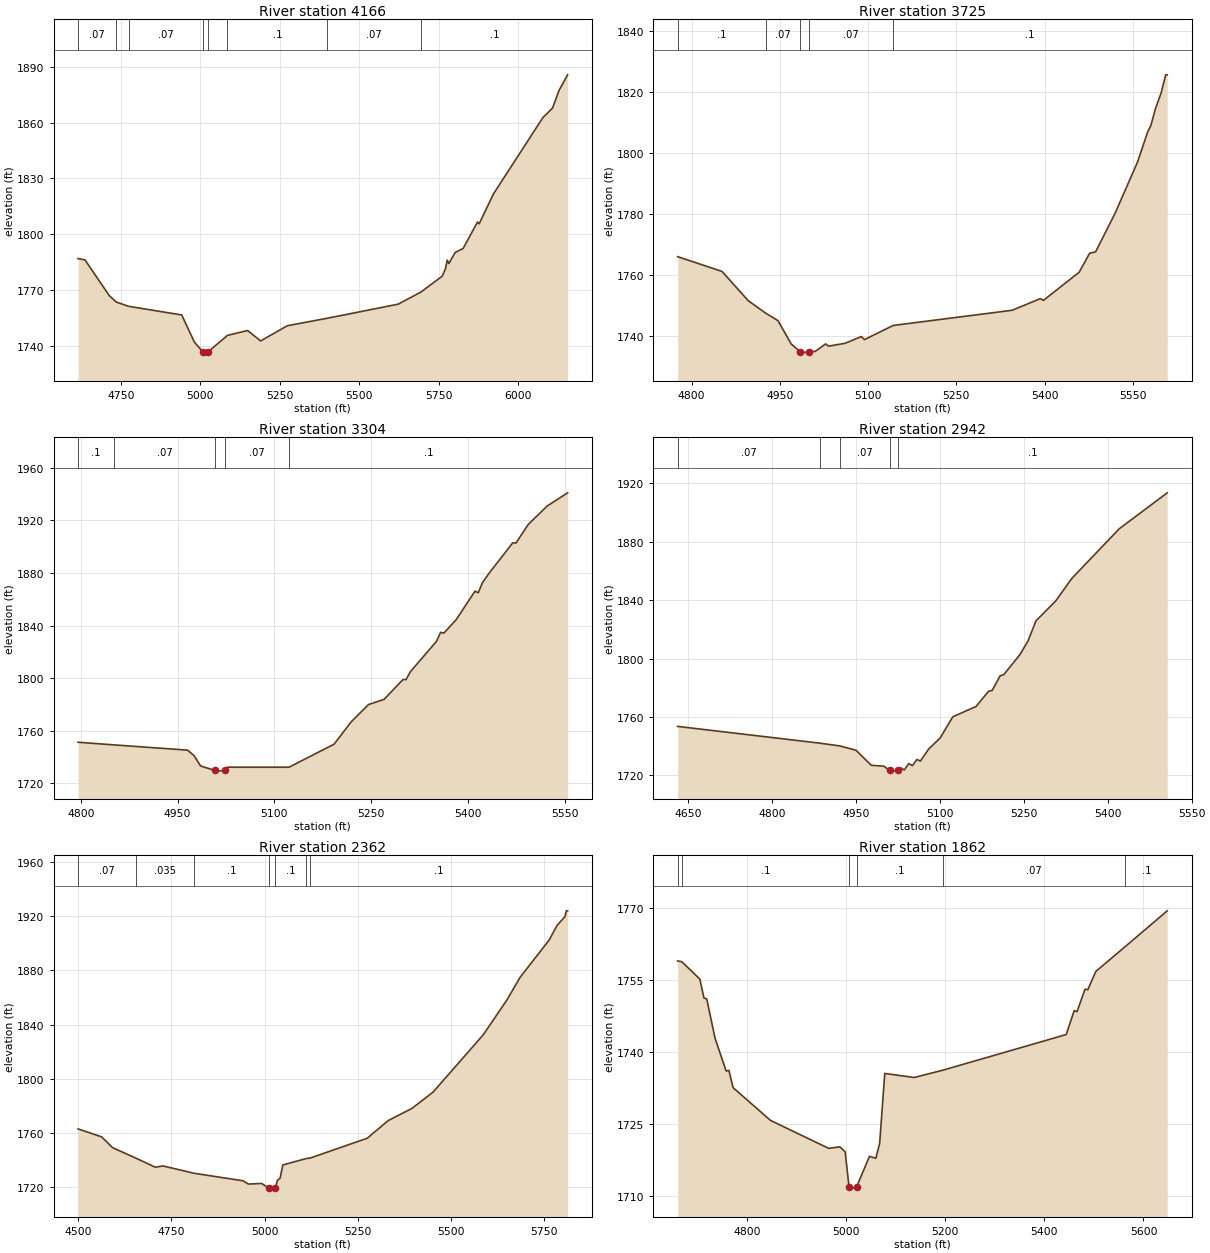
Type RM Length L Ch R = 1,4166,441,441,441
BEGIN DESCRIPTION:
Kelley Creek 9.0
END DESCRIPTION:
XS GIS Cut Line= 4
      1874924.99     13932475.00      1875275.00     13932325.00
      1875941.02     13932189.28      1876411.53     13932286.72
#Sta/Elev= 30
  4615.0 1786.98  4636.8 1786.31  4712.9 1767.21  4735.5 1763.63  4773.9 1761.37
  4941.4 1756.70  4981.3 1742.12  5009.0 1736.71  5009.5 1736.21  5022.9 1736.71
  5085.4 1745.74  5148.9 1748.36  5189.7 1742.75  5273.8 1750.93  5399.0 1754.92
  5622.6 1762.50  5694.7 1769.05  5761.3 1777.56  5771.5 1781.47  5777.1 1786.17
  5782.2 1784.33  5802.1 1790.25  5827.3 1792.47  5872.4 1806.66  5877.5 1805.63
  5922.6 1821.72  6078.3 1862.74  6108.5 1867.81  6128.9 1877.30  6156.0 1885.68
#Mann=8,-1,0
  4615.0    0.07       0  4735.5     0.1       0  4773.9    0.07       0
  5009.0    0.05       0  5022.9    0.07       0  5085.4     0.1       0
  5399.0    0.07       0  5694.7     0.1       0
Bank Sta=5009,5022.9
Exp/Cntr=0.3,0.1

Type RM Length L Ch R = 1,3725,421,421,421
BEGIN DESCRIPTION:
Kelley Creek 8.0
END DESCRIPTION:
XS GIS Cut Line= 3
      1875325.01     13932775.00      1875525.00     13932675.00
      1876125.02     13932775.00
#Sta/Elev= 30
  4776.4 1766.16  4851.9 1761.31  4896.6 1751.68  4926.1 1747.63  4946.9 1745.20
  4969.3 1737.56  4984.2 1735.04  4984.7 1734.54  4999.1 1735.04  5010.1 1735.08
  5027.9 1737.57  5032.9 1736.84  5060.8 1737.75  5088.7 1739.98  5093.8 1738.96
  5142.6 1743.61  5344.7 1748.58  5392.8 1752.42  5397.9 1751.83  5458.7 1761.06
  5476.5 1767.28  5486.6 1767.73  5519.6 1780.34  5557.6 1797.06  5575.3 1807.16
  5580.4 1809.06  5588.0 1814.50  5598.1 1819.94  5605.7 1825.76  5608.3 1825.76
#Mann=5,-1,0
  4776.4     0.1       0  4926.1    0.07       0  4984.2    0.05       0
  4999.1    0.07       0  5142.6     0.1       0
Bank Sta=4984.2,4999.1
Exp/Cntr=0.3,0.1

Type RM Length L Ch R = 1,3304,362,362,362
BEGIN DESCRIPTION:
Kelley Creek 7.0
END DESCRIPTION:
XS GIS Cut Line= 3
      1875525.04     13933025.00      1875725.00     13933025.00
      1876275.02     13932925.00
#Sta/Elev= 30
  4795.6 1751.19  4851.0 1749.18  4965.6 1745.17  4975.6 1740.92  4985.6 1733.11
  5008.3 1729.70  5008.8 1729.20  5023.5 1729.70  5027.3 1732.19  5122.8 1732.20
  5192.5 1749.67  5219.2 1766.78  5245.9 1779.85  5270.0 1783.80  5299.2 1798.79
  5304.3 1798.94  5310.6 1804.73  5351.3 1827.93  5357.7 1834.83  5362.7 1834.19
  5381.8 1844.41  5411.0 1866.15  5416.1 1864.95  5422.4 1872.45  5432.6 1879.64
  5469.5 1902.89  5474.5 1902.76  5493.6 1916.94  5522.8 1930.89  5554.6 1940.98
#Mann=5,-1,0
  4795.6     0.1       0  4851.0    0.07       0  5008.3    0.05       0
  5023.5    0.07       0  5122.8     0.1       0
Bank Sta=5008.3,5023.5
Exp/Cntr=0.3,0.1

Type RM Length L Ch R = 1,2942,580,580,580
BEGIN DESCRIPTION:
Kelley Creek 6.0
END DESCRIPTION:
XS GIS Cut Line= 3
      1875522.83     13933444.28      1875891.92     13933329.09
      1876274.96     13933025.03
#Sta/Elev= 30
  4630.6 1753.58  4884.8 1742.11  4920.7 1740.23  4949.7 1737.25  4977.0 1726.96
  4999.5 1726.37  5009.6 1723.48  5010.1 1722.98  5024.8 1723.48  5029.7 1725.23
  5036.1 1723.78  5044.1 1728.19  5050.5 1726.72  5058.6 1730.93  5064.9 1729.90
  5079.4 1738.00  5100.2 1745.70  5122.7 1760.13  5164.3 1767.20  5186.7 1777.62
  5193.1 1778.16  5207.5 1788.19  5213.9 1788.97  5242.8 1802.66  5257.2 1811.98
  5271.6 1825.82  5306.9 1839.41  5335.7 1854.83  5420.6 1888.82  5506.3 1913.37
#Mann=5,-1,0
  4630.6    0.07       0  4884.8   0.035       0  4920.7    0.07       0
  5009.6    0.05       0  5024.8     0.1       0
Bank Sta=5009.6,5024.8
Exp/Cntr=0.3,0.1

Type RM Length L Ch R = 1,2362,500,500,500
BEGIN DESCRIPTION:
Kelley Creek 5.0
END DESCRIPTION:
XS GIS Cut Line= 3
      1875624.98     13934125.02      1876025.00     13933825.00
      1876625.02     13933274.98
#Sta/Elev= 30
  4499.4 1763.02  4563.0 1757.09  4592.1 1749.15  4654.1 1741.50  4706.7 1734.71
  4727.6 1735.65  4811.3 1730.22  4942.1 1724.70  4956.7 1722.27  4992.1 1722.71
  5013.1 1719.03  5013.6 1718.53  5028.4 1719.03  5034.9 1725.14  5041.7 1726.58
  5049.1 1736.37  5112.3 1741.15  5122.4 1741.47  5275.4 1756.08  5332.1 1769.19
  5395.6 1778.13  5452.3 1790.18  5586.8 1832.43  5650.6 1858.25  5686.0 1874.97
  5763.7 1902.39  5785.3 1913.33  5806.3 1919.75  5810.0 1924.03  5813.4 1924.03
#Mann=7,-1,0
  4499.4    0.07       0  4654.1   0.035       0  4811.3     0.1       0
  5013.1    0.05       0  5028.4     0.1       0  5112.3    0.07       0
  5122.4     0.1       0
Bank Sta=5013.1,5028.4
Exp/Cntr=0.3,0.1

Type RM Length L Ch R = 1,1862,443,443,443
BEGIN DESCRIPTION:
Kelley Creek 4.0
END DESCRIPTION:
XS GIS Cut Line= 4
      1875724.97     13934174.98      1876025.00     13934325.00
      1876225.00     13934275.00      1876616.52     13934060.97
#Sta/Elev= 30
  4660.2 1758.99  4668.7 1758.83  4705.0 1755.21  4713.3 1751.26  4718.9 1751.07
  4735.7 1742.87  4758.1 1736.02  4763.7 1736.16  4772.0 1732.57  4847.5 1725.73
  4964.9 1719.90  4987.3 1720.21  4998.2 1719.19  5006.0 1711.89  5006.5 1711.39
  5021.4 1711.89  5047.2 1718.22  5060.1 1717.83  5067.8 1720.93  5078.1 1735.52
  5137.4 1734.68  5195.2 1736.20  5444.2 1743.64  5460.3 1748.64  5466.0 1748.41
  5482.1 1753.09  5487.8 1753.00  5504.0 1756.81  5563.4 1762.00  5648.0 1769.45
#Mann=6,-1,0
  4660.2    0.07       0  4668.7     0.1       0  5006.0    0.05       0
  5021.4     0.1       0  5195.2    0.07       0  5563.4     0.1       0
Bank Sta=5006,5021.4
Exp/Cntr=0.3,0.1

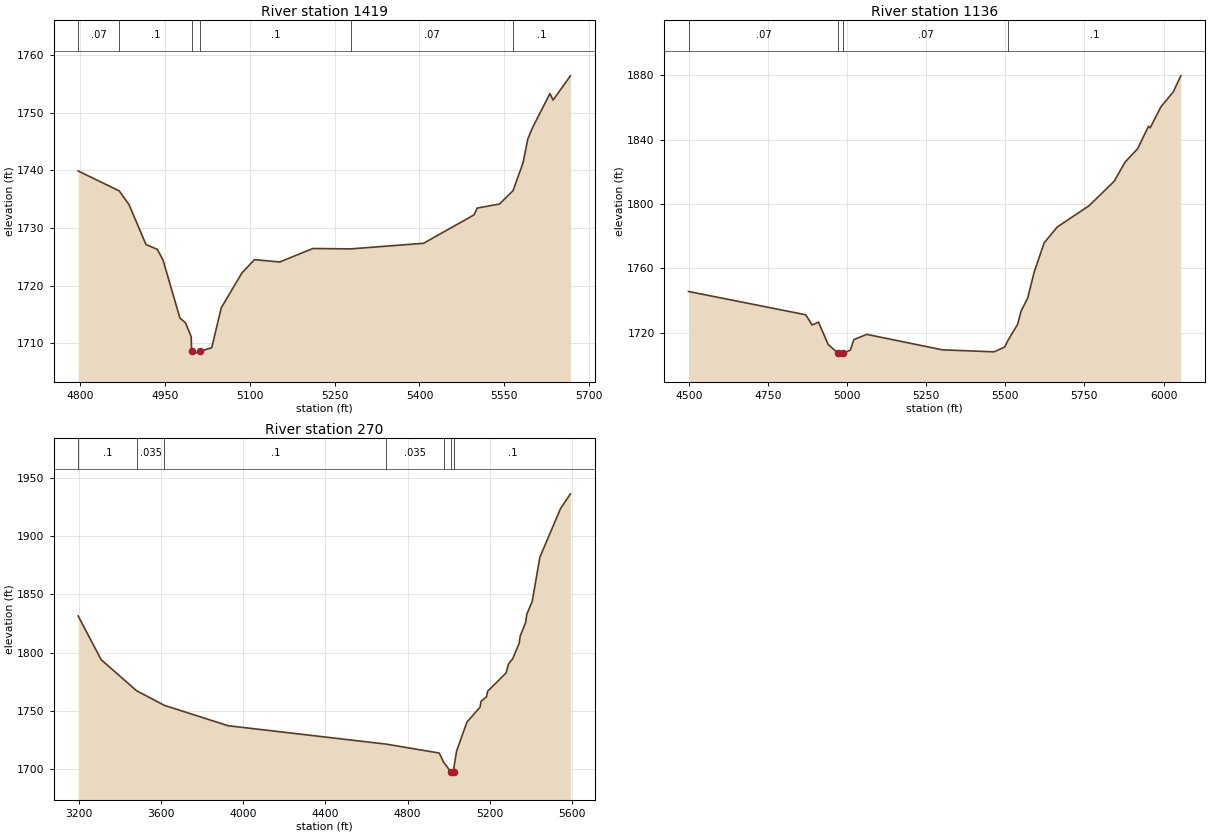
Type RM Length L Ch R = 1,1419,283,283,283
BEGIN DESCRIPTION:
Kelley Creek 3.0
END DESCRIPTION:
XS GIS Cut Line= 3
      1875774.99     13934725.00      1875975.00     13934725.00
      1876574.97     13934425.01
#Sta/Elev= 30
  4796.2 1739.88  4868.8 1736.43  4886.2 1734.04  4916.2 1727.13  4936.2 1726.29
  4946.2 1724.48  4976.2 1714.40  4986.2 1713.54  4996.2 1711.13  4996.9 1708.63
  4997.4 1708.13  5012.3 1708.63  5032.5 1709.25  5049.3 1716.15  5085.7 1722.17
  5108.0 1724.51  5152.7 1724.10  5211.4 1726.44  5278.1 1726.37  5407.1 1727.34
  5496.5 1732.27  5502.1 1733.45  5541.3 1734.14  5565.5 1736.47  5583.2 1741.30
  5591.6 1745.41  5599.9 1747.37  5630.7 1753.30  5636.3 1752.17  5667.0 1756.37
#Mann=6,-1,0
  4796.2    0.07       0  4868.8     0.1       0  4996.9    0.05       0
  5012.3     0.1       0  5278.1    0.07       0  5565.5     0.1       0
Bank Sta=4996.9,5012.3
Exp/Cntr=0.3,0.1

Type RM Length L Ch R = 1,1136,866,866,866
BEGIN DESCRIPTION:
Kelley Creek 2.0
END DESCRIPTION:
XS GIS Cut Line= 3
      1875575.09     13935005.50      1876066.76     13934976.77
      1877091.46     13934693.66
#Sta/Elev= 30
  4499.0 1745.69  4869.5 1731.22  4889.6 1724.85  4909.6 1726.66  4940.4 1712.76
  4972.0 1707.28  4972.5 1706.78  4987.4 1707.28  5010.4 1709.28  5021.5 1715.82
  5062.3 1719.05  5300.9 1709.46  5464.6 1708.20  5498.0 1711.20  5508.9 1715.48
  5538.5 1725.13  5549.9 1733.45  5570.7 1741.59  5591.4 1757.82  5622.7 1775.84
  5664.0 1785.71  5765.3 1799.04  5844.3 1814.20  5878.7 1826.12  5918.2 1834.34
  5952.5 1848.32  5957.7 1847.31  5992.0 1860.42  6030.8 1869.68  6054.6 1879.63
#Mann=4,-1,0
  4499.0    0.07       0  4972.0    0.05       0  4987.4    0.07       0
  5508.9     0.1       0
Bank Sta=4972,4987.4
Exp/Cntr=0.3,0.1

Type RM Length L Ch R = 1,270,0,0,0
BEGIN DESCRIPTION:
Kelley Creek 1.0
END DESCRIPTION:
XS GIS Cut Line= 4
      1875005.02     13935083.25      1875950.66     13935306.50
      1876727.06     13935042.52      1877301.44     13934853.41
#Sta/Elev= 30
  3196.0 1831.50  3308.1 1793.83  3480.2 1767.17  3615.6 1754.54  3926.2 1737.00
  4695.5 1721.17  4953.8 1713.49  4974.6 1705.72  5009.3 1697.56  5009.8 1697.06
  5025.0 1697.56  5025.1 1700.84  5026.9 1703.04  5038.2 1715.16  5088.6 1740.15
  5152.2 1752.93  5157.4 1758.00  5184.0 1762.00  5189.2 1766.65  5279.3 1782.46
  5290.8 1790.18  5311.1 1794.59  5342.9 1807.95  5348.1 1814.32  5374.6 1826.00
  5379.9 1833.01  5406.4 1844.01  5443.5 1882.04  5544.1 1923.88  5592.4 1936.63
#Mann=8,-1,0
  3196.0     0.1       0  3480.2   0.035       0  3615.6     0.1       0
  4695.5   0.035       0  4974.6    0.07       0  5009.3    0.05       0
  5025.0    0.07       0  5026.9     0.1       0
Bank Sta=5009.3,5025
Exp/Cntr=0.3,0.1

Chan Stop Cuts=-1