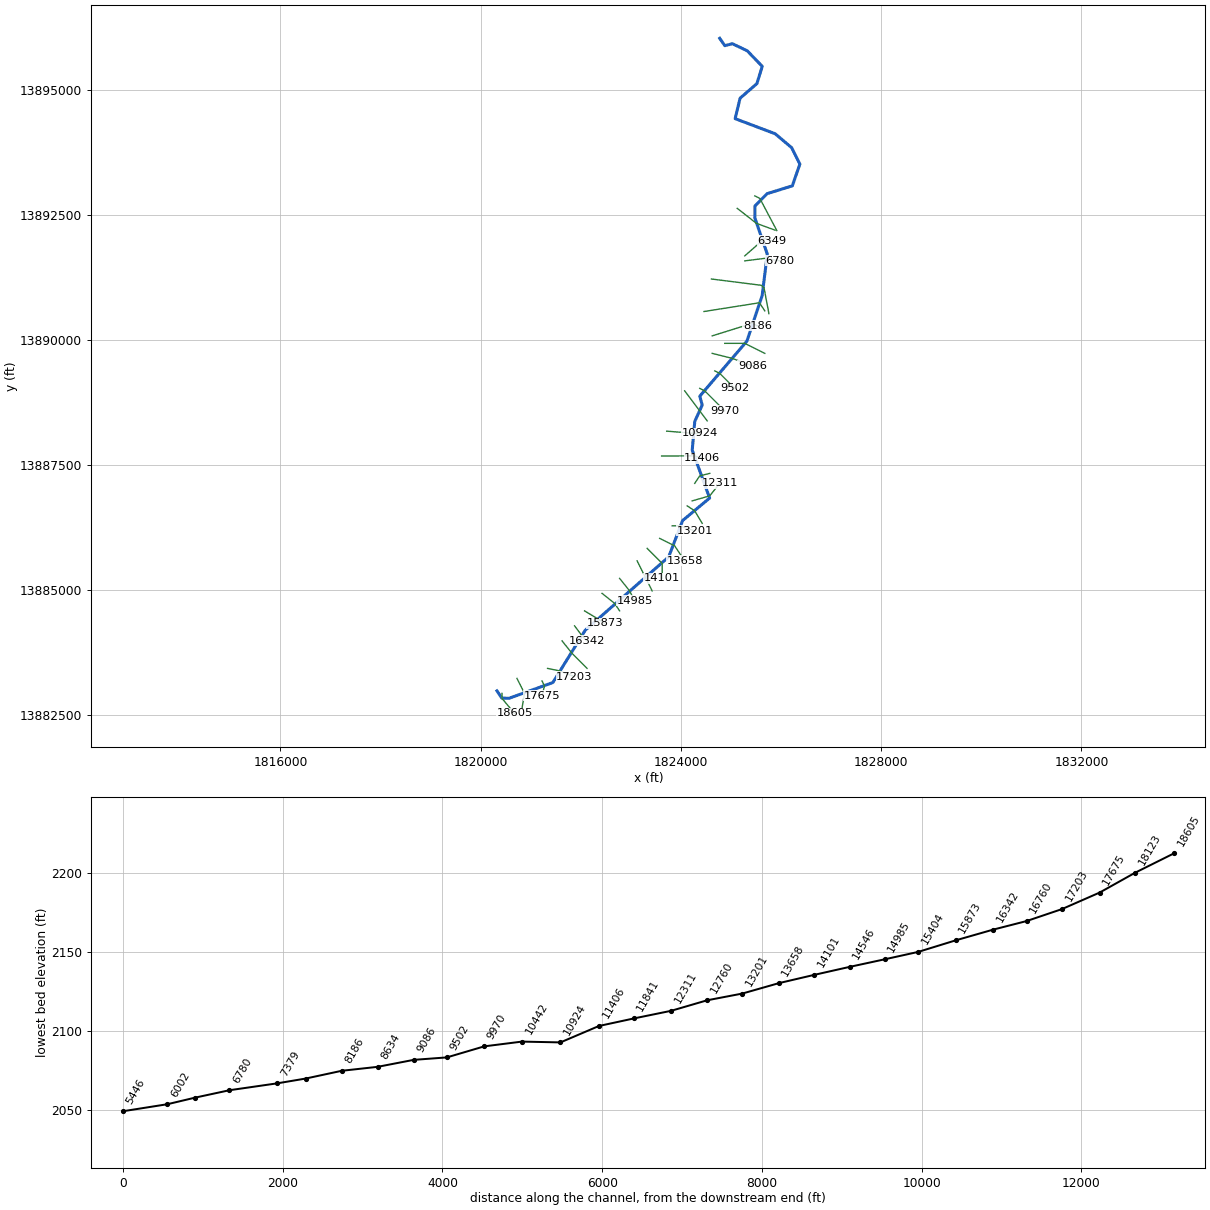
--- Mullen Creek.prj (project) ---

Proj Title=Mullen Creek Base Level Engineering
Current Plan=p01
Default Exp/Contr=0.3,0.1
English Units
Geom File=g01
Flow File=f01
Plan File=p01
BEGIN DESCRIPTION:
Mullen Creek
END DESCRIPTION:

--- Mullen Creek.p01 (plan) ---

Plan Title=Multiple Run
Short Identifier=Multiple
Geom File=g01
Flow File=f01
Subcritical Flow
K Sum by GR= 0
Std Step Tol= 0.01
Critical Tol= 0.01
Num of Std Step Trials= 20
Max Error Tol= 0.3
Flow Tol Ratio= 0.001
Split Flow NTrial= 30
Split Flow Tol= 0.02
Split Flow Ratio= 0.02
Log Output Level= 0
Friction Slope Method= 1
Unsteady Friction Slope Method= 2
Unsteady Bridges Friction Slope Method= 1
Parabolic Critical Depth
Global Vel Dist=  1 , 1 , 1
Global Log Level= 0
CheckData=True
Encroach Param= -1, 0, 0, 0
BEGIN DESCRIPTION:
Multiple Run
END DESCRIPTION:

--- Mullen Creek.f01 (steady flow) ---

Flow Title=Multiple
Number of Profiles=7
Profile Names=10-year,25-year,50-year,1pct_min,100-year,1pct_plu,500-year
River Rch & RM= Mullen Creek,Reach-1,18605
     380     610     816     531    1060    2114    1759
River Rch & RM= Mullen Creek,Reach-1,17203
    1533    2682    3801    2601    5189   10354    9568
River Rch & RM= Mullen Creek,Reach-1,11841
    2018    3568    5090    3501    6986   13938   13024
River Rch & RM= Mullen Creek,Reach-1,6780
    2694    4826    6947    4817    9610   19175   18209
River Rch & RM= Mullen Creek,Reach-1,4574
    3422    6193    8974    6258   12486   24914   23938
River Rch & RM= Mullen Creek,Reach-1,690
    3338    6058    8792    6140   12251   24444   23568
River Rch & RM= Mullen Creek,Reach-1,163
    3450    6270    9109    6368   12705   25351   24490
Boundary for River Rch & Prof#=Mullen Creek,Reach-1,1
Up Type=0
Dn Type=3
Dn Slope=0.005
Boundary for River Rch & Prof#=Mullen Creek,Reach-1,2
Up Type=0
Dn Type=3
Dn Slope=0.005
Boundary for River Rch & Prof#=Mullen Creek,Reach-1,3
Up Type=0
Dn Type=3
Dn Slope=0.005
Boundary for River Rch & Prof#=Mullen Creek,Reach-1,4
Up Type=0
Dn Type=3
Dn Slope=0.005
Boundary for River Rch & Prof#=Mullen Creek,Reach-1,5
Up Type=0
Dn Type=3
Dn Slope=0.005
Boundary for River Rch & Prof#=Mullen Creek,Reach-1,6
Up Type=0
Dn Type=3
Dn Slope=0.005
Boundary for River Rch & Prof#=Mullen Creek,Reach-1,7
Up Type=0
Dn Type=3
Dn Slope=0.005

--- Mullen Creek.g01 (geometry) ---

Geom Title=Existing Conditions

River Reach=Mullen Creek,Reach-1
Reach XY= 30
      1820325.00     13882975.00      1820422.53     13882830.44
      1820564.49     13882826.21      1821441.68     13883141.64
      1822088.63     13884188.21      1823755.22     13885654.91
      1824033.14     13886381.06      1824573.04     13886830.89
      1824225.51     13887790.22      1824276.20     13888364.50
      1824424.91     13888690.39      1824376.96     13888869.11
      1825316.87     13889968.93      1825622.74     13890880.94
      1825724.85     13891709.58      1825477.26     13892430.94
      1825478.75     13892673.45      1825722.71     13892919.15
      1826225.00     13893075.00      1826375.72     13893509.94
      1826211.37     13893838.21      1825881.17     13894117.14
      1825082.67     13894418.48      1825180.83     13894827.30
      1825516.85     13895118.93      1825623.95     13895464.56
      1825325.00     13895775.00      1825028.38     13895917.40
      1824876.01     13895878.03      1824775.00     13896025.00

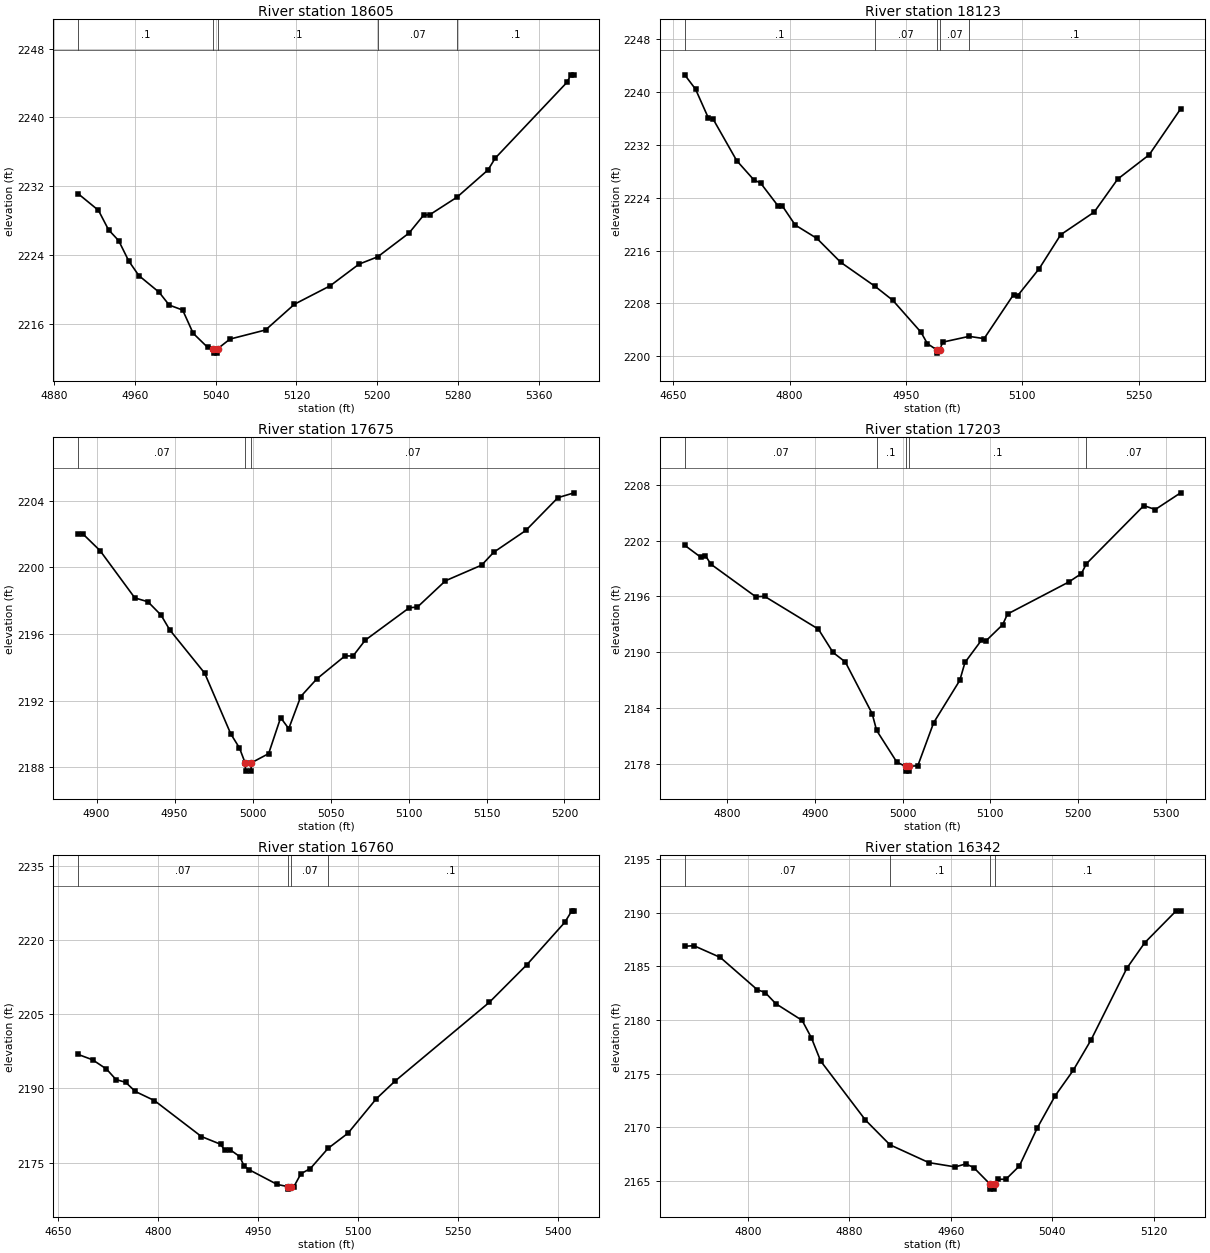
Type RM Length L Ch R = 1,18605,482,482,482
BEGIN DESCRIPTION:
Mullen Creek 41.0
END DESCRIPTION:
XS GIS Cut Line= 3
      1820425.00     13882925.03      1820425.00     13882825.00
      1820674.97     13882525.03
#Sta/Elev= 30
  4904.2 2231.14  4924.2 2229.22  4934.2 2226.96  4944.2 2225.70  4954.2 2223.33
  4964.2 2221.64  4984.2 2219.71  4994.2 2218.22  5007.5 2217.64  5017.9 2214.94
  5032.2 2213.31  5038.0 2213.14  5038.3 2212.64  5041.8 2212.64  5042.0 2213.14
  5054.3 2214.27  5089.5 2215.33  5118.1 2218.32  5153.3 2220.45  5181.9 2222.97
  5200.4 2223.82  5231.4 2226.58  5245.7 2228.64  5252.2 2228.73  5278.9 2230.75
  5309.5 2233.91  5316.6 2235.27  5387.6 2244.08  5391.5 2244.95  5394.7 2244.95
#Mann=5,-1,0
  4904.2     0.1       0  5038.0    0.05       0  5042.0     0.1       0
  5200.4    0.07       0  5278.9     0.1       0
Bank Sta=5038,5042
Exp/Cntr=0.3,0.1

Type RM Length L Ch R = 1,18123,448,448,448
BEGIN DESCRIPTION:
Mullen Creek 40.0
END DESCRIPTION:
XS GIS Cut Line= 3
      1820725.00     13883224.99      1820875.00     13882925.00
      1820825.01     13882625.04
#Sta/Elev= 30
  4664.6 2242.63  4678.6 2240.46  4695.3 2236.05  4700.9 2236.00  4731.7 2229.63
  4754.0 2226.69  4762.4 2226.25  4784.8 2222.80  4790.4 2222.79  4807.1 2219.88
  4835.1 2217.85  4865.8 2214.23  4910.3 2210.57  4932.9 2208.48  4969.3 2203.64
  4977.6 2201.90  4989.6 2200.97  4989.9 2200.47  4993.6 2200.97  4997.2 2202.13
  5031.3 2203.01  5050.7 2202.67  5088.7 2209.34  5093.8 2209.15  5121.7 2213.26
  5149.5 2218.41  5192.6 2221.83  5223.0 2226.84  5263.6 2230.52  5304.1 2237.47
#Mann=5,-1,0
  4664.6     0.1       0  4910.3    0.07       0  4989.6    0.05       0
  4993.6    0.07       0  5031.3     0.1       0
Bank Sta=4989.6,4993.6
Exp/Cntr=0.3,0.1

Type RM Length L Ch R = 1,17675,472,472,472
BEGIN DESCRIPTION:
Mullen Creek 39.0
END DESCRIPTION:
XS GIS Cut Line= 3
      1821225.00     13883175.00      1821275.00     13883075.00
      1821224.99     13882874.96
#Sta/Elev= 30
  4888.2 2202.03  4891.0 2202.03  4902.2 2201.01  4924.5 2198.17  4932.9 2197.94
  4941.3 2197.14  4946.9 2196.25  4969.3 2193.65  4986.0 2190.01  4991.6 2189.16
  4995.2 2188.27  4995.5 2187.77  4999.0 2187.77  4999.2 2188.27  5010.3 2188.82
  5018.0 2190.98  5023.2 2190.32  5030.9 2192.25  5041.2 2193.31  5059.3 2194.69
  5064.4 2194.68  5072.2 2195.63  5100.5 2197.58  5105.7 2197.62  5123.7 2199.20
  5146.9 2200.14  5154.6 2200.91  5175.2 2202.22  5195.8 2204.19  5206.2 2204.48
#Mann=3,-1,0
  4888.2    0.07       0  4995.2    0.05       0  4999.2    0.07       0
Bank Sta=4995.2,4999.2
Exp/Cntr=0.3,0.1

Type RM Length L Ch R = 1,17203,443,443,443
BEGIN DESCRIPTION:
Mullen Creek 38.0
END DESCRIPTION:
XS GIS Cut Line= 3
      1821335.74     13883424.60      1821575.00     13883375.00
      1821874.01     13883258.38
#Sta/Elev= 30
  4751.5 2201.49  4770.1 2200.19  4775.2 2200.37  4781.4 2199.46  4832.4 2195.98
  4842.7 2196.01  4903.9 2192.50  4920.6 2190.00  4934.6 2188.98  4965.2 2183.44
  4970.3 2181.64  4993.3 2178.25  5003.4 2177.78  5003.7 2177.28  5007.2 2177.28
  5007.4 2177.78  5017.3 2177.87  5035.3 2182.47  5065.1 2187.01  5071.0 2188.93
  5089.6 2191.29  5095.0 2191.25  5113.9 2192.97  5119.5 2194.12  5189.1 2197.54
  5203.7 2198.45  5209.4 2199.51  5274.9 2205.74  5287.9 2205.32  5316.8 2207.11
#Mann=5,-1,0
  4751.5    0.07       0  4970.3     0.1       0  5003.4    0.05       0
  5007.4     0.1       0  5209.4    0.07       0
Bank Sta=5003.4,5007.4
Exp/Cntr=0.3,0.1

Type RM Length L Ch R = 1,16760,418,418,418
BEGIN DESCRIPTION:
Mullen Creek 37.0
END DESCRIPTION:
XS GIS Cut Line= 3
      1821624.99     13883975.01      1821825.00     13883725.00
      1822124.98     13883425.02
#Sta/Elev= 30
  4679.6 2196.87  4701.2 2195.79  4722.0 2193.93  4736.4 2191.79  4750.8 2191.25
  4765.3 2189.40  4794.1 2187.55  4864.5 2180.30  4893.3 2178.74  4899.7 2177.50
  4907.7 2177.63  4922.1 2176.24  4928.5 2174.36  4935.7 2173.63  4978.2 2170.63
  4994.6 2170.18  4994.8 2169.68  4998.6 2170.18  5003.3 2170.18  5013.9 2172.79
  5028.1 2173.84  5054.6 2177.91  5084.6 2180.98  5127.0 2187.92  5155.3 2191.51
  5296.8 2207.41  5353.3 2215.03  5409.9 2223.54  5420.5 2225.87  5424.0 2225.87
#Mann=4,-1,0
  4679.6    0.07       0  4994.6    0.05       0  4998.6    0.07       0
  5054.6     0.1       0
Bank Sta=4994.6,4998.6
Exp/Cntr=0.3,0.1

Type RM Length L Ch R = 1,16342,469,469,469
BEGIN DESCRIPTION:
Mullen Creek 36.0
END DESCRIPTION:
XS GIS Cut Line= 3
      1821875.01     13884274.99      1822025.00     13884075.00
      1822124.99     13883975.01
#Sta/Elev= 30
  4750.0 2186.88  4757.3 2186.93  4778.1 2185.84  4807.3 2182.83  4813.5 2182.57
  4821.9 2181.53  4842.7 2179.97  4850.0 2178.35  4857.3 2176.19  4892.7 2170.68
  4912.0 2168.38  4942.7 2166.72  4963.5 2166.32  4971.9 2166.60  4978.1 2166.26
  4990.7 2164.75  4990.9 2164.25  4994.4 2164.25  4994.7 2164.75  4996.9 2165.17
  5003.5 2165.17  5014.1 2166.40  5028.3 2169.96  5042.4 2172.95  5056.6 2175.31
  5070.7 2178.15  5099.0 2184.84  5113.1 2187.21  5137.9 2190.18  5141.4 2190.18
#Mann=4,-1,0
  4750.0    0.07       0  4912.0     0.1       0  4990.7    0.05       0
  4994.7     0.1       0
Bank Sta=4990.7,4994.7
Exp/Cntr=0.3,0.1

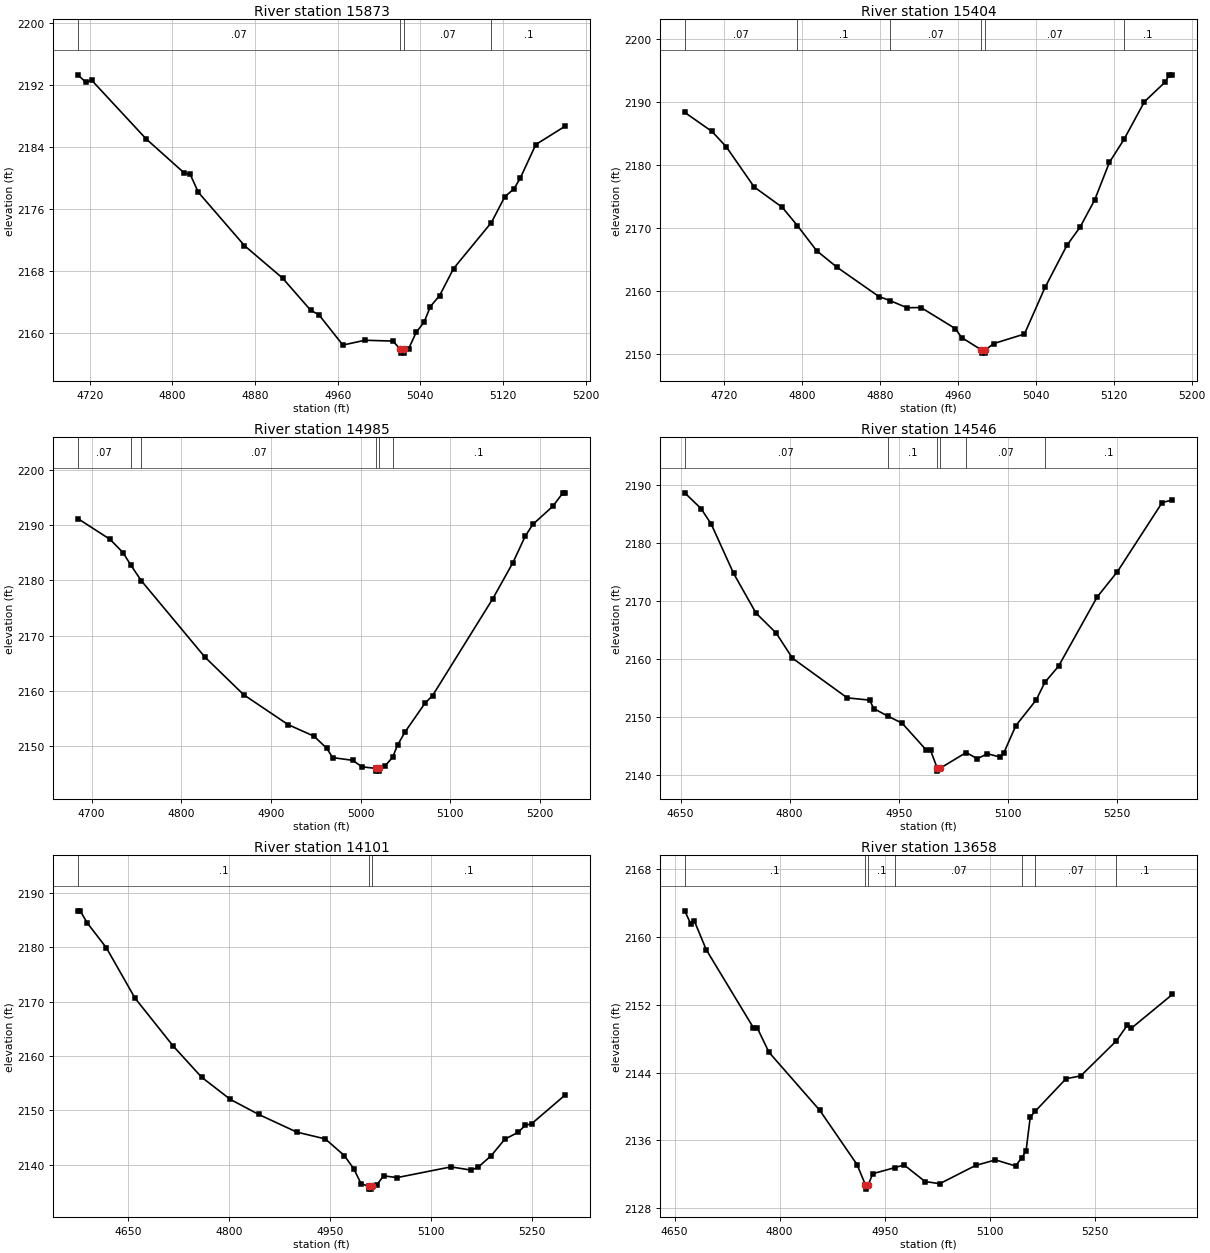
Type RM Length L Ch R = 1,15873,469,469,469
BEGIN DESCRIPTION:
Mullen Creek 35.0
END DESCRIPTION:
XS GIS Cut Line= 3
      1822075.04     13884574.98      1822325.00     13884425.00
      1822475.02     13884324.99
#Sta/Elev= 30
  4708.5 2193.31  4716.2 2192.36  4722.1 2192.59  4774.5 2185.07  4811.5 2180.66
  4817.3 2180.48  4825.1 2178.18  4869.8 2171.30  4906.7 2167.11  4933.9 2162.96
  4941.7 2162.41  4965.0 2158.49  4986.4 2159.11  5013.5 2159.00  5020.5 2157.95
  5020.8 2157.45  5024.3 2157.45  5024.5 2157.95  5028.5 2157.98  5036.1 2160.17
  5043.6 2161.44  5049.6 2163.44  5058.6 2164.86  5072.1 2168.35  5108.7 2174.28
  5121.7 2177.60  5130.7 2178.64  5136.7 2180.02  5151.7 2184.33  5180.3 2186.71
#Mann=4,-1,0
  4708.5    0.07       0  5020.5    0.05       0  5024.5    0.07       0
  5108.7     0.1       0
Bank Sta=5020.5,5024.5
Exp/Cntr=0.3,0.1

Type RM Length L Ch R = 1,15404,419,419,419
BEGIN DESCRIPTION:
Mullen Creek 34.0
END DESCRIPTION:
XS GIS Cut Line= 3
      1822424.98     13884925.02      1822675.00     13884725.00
      1822775.02     13884574.97
#Sta/Elev= 30
  4679.6 2188.34  4707.6 2185.31  4722.1 2182.90  4750.9 2176.49  4779.7 2173.27
  4795.3 2170.35  4814.9 2166.39  4835.7 2163.77  4878.9 2159.10  4890.2 2158.46
  4907.7 2157.32  4922.1 2157.35  4957.4 2154.00  4963.8 2152.59  4984.2 2150.61
  4984.4 2150.11  4987.9 2150.11  4988.2 2150.61  4996.6 2151.62  5028.3 2153.14
  5049.4 2160.54  5071.9 2167.23  5085.4 2170.12  5100.4 2174.44  5115.5 2180.41
  5130.5 2184.06  5151.5 2190.05  5172.6 2193.14  5177.1 2194.31  5180.1 2194.31
#Mann=6,-1,0
  4679.6    0.07       0  4795.3     0.1       0  4890.2    0.07       0
  4984.2    0.05       0  4988.2    0.07       0  5130.5     0.1       0
Bank Sta=4984.2,4988.2
Exp/Cntr=0.3,0.1

Type RM Length L Ch R = 1,14985,439,439,439
BEGIN DESCRIPTION:
Mullen Creek 33.0
END DESCRIPTION:
XS GIS Cut Line= 3
      1822775.01     13885224.99      1822975.00     13884975.00
      1823074.98     13884775.04
#Sta/Elev= 30
  4684.7 2191.21  4720.7 2187.43  4735.1 2185.04  4743.6 2182.83  4755.4 2179.96
  4826.4 2166.10  4869.6 2159.28  4919.2 2153.85  4948.0 2151.76  4962.4 2149.55
  4968.8 2147.87  4991.2 2147.38  5001.6 2146.20  5016.8 2145.92  5017.1 2145.42
  5020.6 2145.42  5020.8 2145.92  5027.2 2146.36  5035.7 2147.91  5041.2 2150.12
  5049.6 2152.52  5071.9 2157.74  5080.3 2159.11  5147.4 2176.66  5169.8 2183.18
  5183.7 2188.03  5192.1 2190.15  5214.5 2193.45  5225.7 2195.87  5228.4 2195.87
#Mann=6,-1,0
  4684.7    0.07       0  4743.6     0.1       0  4755.4    0.07       0
  5016.8    0.05       0  5020.8    0.07       0  5035.7     0.1       0
Bank Sta=5016.8,5020.8
Exp/Cntr=0.3,0.1

Type RM Length L Ch R = 1,14546,445,445,445
BEGIN DESCRIPTION:
Mullen Creek 32.0
END DESCRIPTION:
XS GIS Cut Line= 3
      1823124.99     13885575.03      1823275.00     13885275.00
      1823425.02     13884974.96
#Sta/Elev= 30
  4655.7 2188.66  4678.1 2185.94  4692.1 2183.27  4722.8 2174.78  4753.6 2167.92
  4781.5 2164.45  4803.9 2160.11  4879.3 2153.26  4910.1 2152.87  4915.7 2151.42
  4934.7 2150.13  4954.8 2148.89  4988.3 2144.21  4993.9 2144.21  5003.1 2141.11
  5003.4 2140.61  5007.1 2141.11  5042.9 2143.82  5058.2 2142.76  5072.2 2143.61
  5089.0 2143.06  5094.6 2143.72  5111.3 2148.47  5139.3 2152.90  5151.1 2155.92
  5170.0 2158.72  5223.1 2170.66  5251.1 2175.06  5312.6 2186.98  5326.6 2187.42
#Mann=6,-1,0
  4655.7    0.07       0  4934.7     0.1       0  5003.1    0.05       0
  5007.1     0.1       0  5042.9    0.07       0  5151.1     0.1       0
Bank Sta=5003.1,5007.1
Exp/Cntr=0.3,0.1

Type RM Length L Ch R = 1,14101,443,443,443
BEGIN DESCRIPTION:
Mullen Creek 31.0
END DESCRIPTION:
XS GIS Cut Line= 3
      1823325.00     13885825.00      1823625.00     13885525.00
      1823625.00     13885224.97
#Sta/Elev= 30
  4575.7 2186.71  4579.2 2186.71  4589.8 2184.47  4618.1 2179.92  4660.6 2170.67
  4717.1 2161.88  4759.6 2156.11  4802.0 2152.05  4844.4 2149.26  4901.0 2146.01
  4943.4 2144.75  4971.7 2141.68  4985.8 2139.23  4996.4 2136.54  5008.0 2136.02
  5008.2 2135.52  5011.7 2135.52  5012.0 2136.02  5020.0 2136.32  5030.0 2137.97
  5050.0 2137.64  5130.0 2139.61  5160.0 2139.02  5170.0 2139.51  5190.0 2141.70
  5210.0 2144.70  5230.0 2145.98  5240.0 2147.23  5250.0 2147.56  5300.0 2152.87
#Mann=3,-1,0
  4575.7     0.1       0  5008.0    0.05       0  5012.0     0.1       0
Bank Sta=5008,5012
Exp/Cntr=0.3,0.1

Type RM Length L Ch R = 1,13658,457,457,457
BEGIN DESCRIPTION:
Mullen Creek 30.0
END DESCRIPTION:
XS GIS Cut Line= 3
      1823575.03     13886024.98      1823875.00     13885875.00
      1824074.98     13885575.03
#Sta/Elev= 30
  4664.6 2163.10  4673.0 2161.59  4678.5 2161.86  4695.3 2158.51  4762.4 2149.33
  4768.0 2149.30  4784.8 2146.41  4857.4 2139.55  4910.5 2133.16  4922.5 2130.76
  4922.8 2130.26  4926.5 2130.76  4932.9 2132.08  4965.1 2132.81  4977.6 2133.12
  5007.5 2131.16  5028.5 2130.90  5079.6 2133.05  5108.1 2133.71  5136.7 2132.99
  5145.3 2133.92  5151.7 2134.76  5157.7 2138.75  5164.9 2139.46  5208.8 2143.29
  5229.8 2143.62  5280.6 2147.75  5295.9 2149.57  5301.9 2149.24  5360.5 2153.23
#Mann=7,-1,0
  4664.6     0.1       0  4922.5    0.05       0  4926.5     0.1       0
  4965.1    0.07       0  5145.3     0.1       0  5164.9    0.07       0
  5280.6     0.1       0
Bank Sta=4922.5,4926.5
Exp/Cntr=0.3,0.1

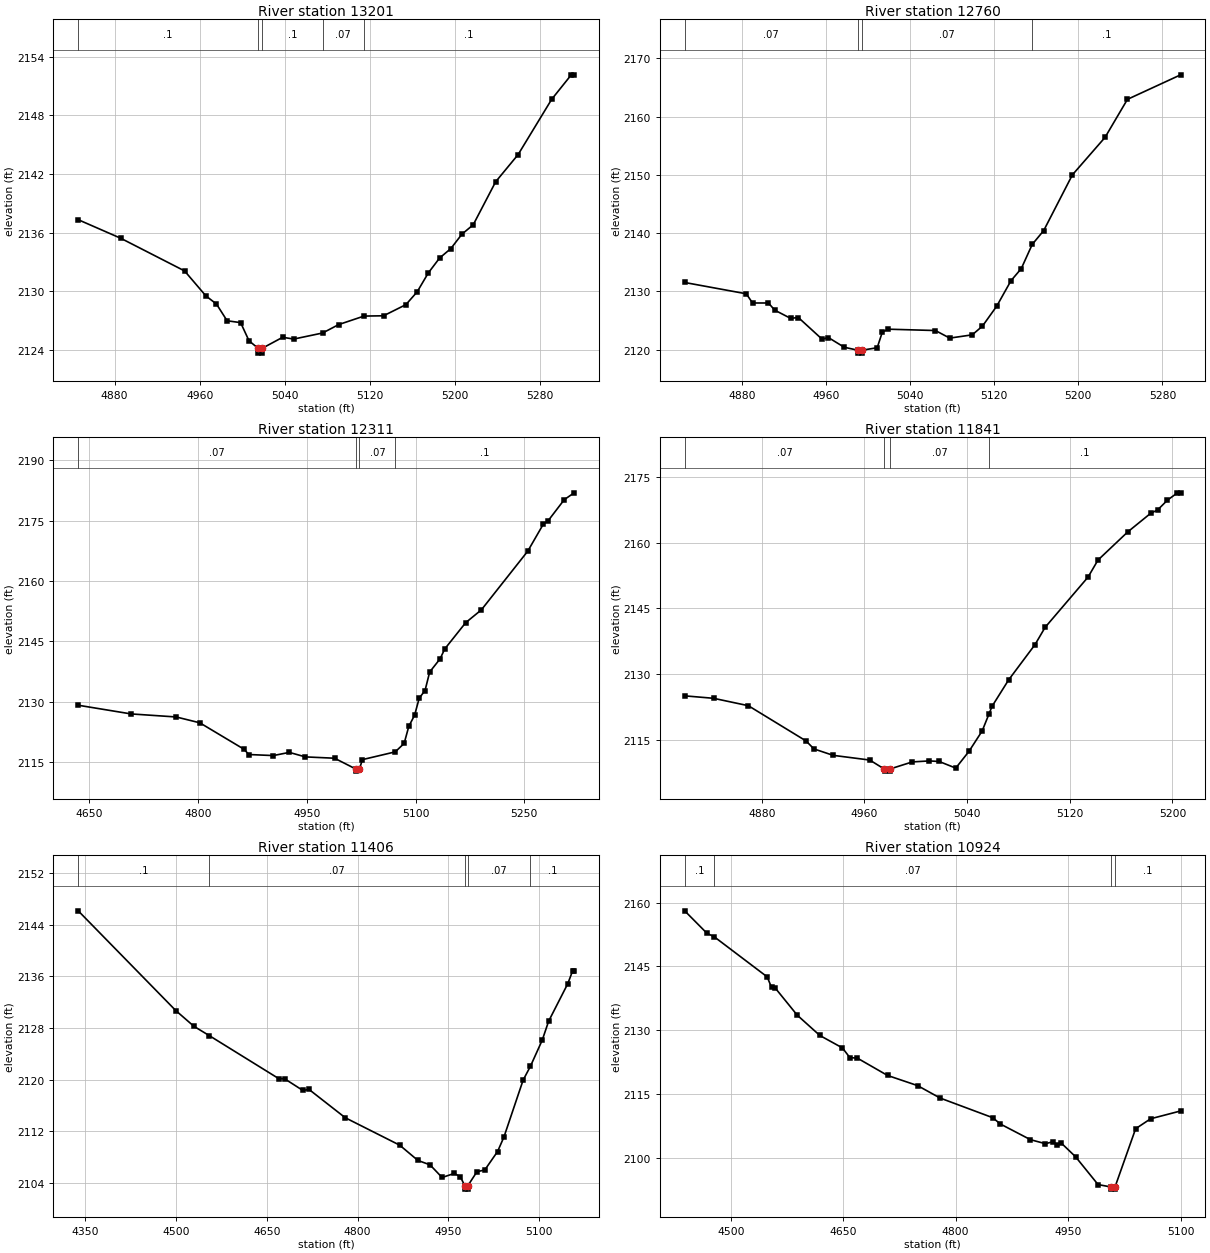
Type RM Length L Ch R = 1,13201,441,441,441
BEGIN DESCRIPTION:
Mullen Creek 29.0
END DESCRIPTION:
XS GIS Cut Line= 3
      1823824.97     13886275.00      1823975.00     13886275.00
      1824275.04     13886174.99
#Sta/Elev= 30
  4845.8 2137.31  4885.8 2135.41  4945.8 2132.07  4965.8 2129.52  4975.8 2128.68
  4985.8 2126.97  4998.5 2126.78  5006.4 2124.92  5014.9 2124.16  5015.2 2123.66
  5018.7 2123.66  5018.9 2124.16  5038.0 2125.28  5048.5 2125.10  5075.6 2125.72
  5090.7 2126.58  5114.5 2127.45  5132.9 2127.48  5153.9 2128.62  5164.5 2129.93
  5175.0 2131.87  5185.6 2133.39  5196.1 2134.35  5206.6 2135.83  5217.2 2136.79
  5238.3 2141.19  5259.4 2143.97  5291.0 2149.63  5309.4 2152.13  5312.1 2152.13
#Mann=5,-1,0
  4845.8     0.1       0  5014.9    0.05       0  5018.9     0.1       0
  5075.6    0.07       0  5114.5     0.1       0
Bank Sta=5014.9,5018.9
Exp/Cntr=0.3,0.1

Type RM Length L Ch R = 1,12760,449,449,449
BEGIN DESCRIPTION:
Mullen Creek 28.0
END DESCRIPTION:
XS GIS Cut Line= 3
      1824124.96     13886675.02      1824275.00     13886575.00
      1824425.02     13886324.97
#Sta/Elev= 30
  4825.4 2131.51  4884.0 2129.57  4890.0 2127.99  4905.1 2127.99  4911.1 2126.76
  4926.1 2125.36  4933.6 2125.49  4956.1 2121.78  4962.2 2122.05  4977.2 2120.39
  4990.2 2119.88  4990.5 2119.38  4994.0 2119.38  4994.2 2119.88  5008.6 2120.31
  5013.5 2123.01  5019.3 2123.49  5064.0 2123.26  5077.6 2121.96  5099.0 2122.52
  5108.7 2124.01  5122.3 2127.44  5135.9 2131.82  5145.7 2133.90  5156.1 2138.05
  5167.0 2140.42  5194.3 2149.99  5225.4 2156.43  5246.7 2162.96  5297.3 2167.17
#Mann=4,-1,0
  4825.4    0.07       0  4990.2    0.05       0  4994.2    0.07       0
  5156.1     0.1       0
Bank Sta=4990.2,4994.2
Exp/Cntr=0.3,0.1

Type RM Length L Ch R = 1,12311,470,470,470
BEGIN DESCRIPTION:
Mullen Creek 27.0
END DESCRIPTION:
XS GIS Cut Line= 3
      1824225.03     13886775.01      1824575.00     13886875.00
      1824774.98     13887124.98
#Sta/Elev= 30
  4634.7 2129.11  4707.5 2126.95  4769.9 2126.19  4802.4 2124.74  4863.5 2118.15
  4870.0 2116.85  4903.8 2116.59  4925.9 2117.38  4948.0 2116.26  4988.3 2115.93
  5017.9 2113.22  5018.3 2112.72  5022.6 2113.22  5026.7 2115.58  5072.0 2117.51
  5084.3 2119.62  5090.7 2123.85  5098.7 2126.63  5105.1 2130.88  5113.1 2132.77
  5119.5 2137.37  5133.9 2140.66  5140.3 2143.11  5169.2 2149.65  5190.8 2152.83
  5254.8 2167.43  5276.4 2174.19  5282.8 2174.97  5305.2 2180.25  5318.8 2181.94
#Mann=4,-1,0
  4634.7    0.07       0  5017.9    0.05       0  5022.6    0.07       0
  5072.0     0.1       0
Bank Sta=5017.9,5022.6
Exp/Cntr=0.3,0.1

Type RM Length L Ch R = 1,11841,435,435,435
BEGIN DESCRIPTION:
Mullen Creek 26.0
END DESCRIPTION:
XS GIS Cut Line= 3
      1824275.00     13887125.00      1824375.00     13887275.00
      1824574.97     13887324.99
#Sta/Elev= 30
  4820.0 2125.02  4842.5 2124.46  4869.6 2122.77  4914.6 2114.72  4920.7 2112.91
  4935.7 2111.44  4964.2 2110.37  4975.4 2108.34  4975.7 2107.84  4979.7 2107.84
  4980.1 2108.34  4997.3 2109.94  5010.6 2110.17  5018.3 2110.04  5031.2 2108.53
  5041.5 2112.35  5051.8 2117.02  5057.2 2120.96  5059.5 2122.64  5072.4 2128.66
  5093.0 2136.73  5100.8 2140.64  5134.3 2152.13  5142.0 2156.00  5165.2 2162.43
  5183.2 2166.71  5188.4 2167.42  5196.1 2169.67  5203.9 2171.35  5206.4 2171.35
#Mann=4,-1,0
  4820.0    0.07       0  4975.4    0.05       0  4980.1    0.07       0
  5057.2     0.1       0
Bank Sta=4975.4,4980.1
Exp/Cntr=0.3,0.1

Type RM Length L Ch R = 1,11406,482,482,482
BEGIN DESCRIPTION:
Mullen Creek 25.0
END DESCRIPTION:
XS GIS Cut Line= 3
      1823613.93     13887672.38      1824275.00     13887675.00
      1824425.01     13887625.00
#Sta/Elev= 30
  4338.5 2146.14  4499.6 2130.71  4529.6 2128.27  4554.8 2126.84  4669.6 2120.18
  4679.6 2120.14  4709.6 2118.34  4719.6 2118.51  4779.6 2114.12  4869.6 2109.87
  4899.6 2107.51  4919.6 2106.83  4939.6 2104.87  4959.6 2105.50  4969.6 2105.00
  4977.2 2103.57  4977.5 2103.07  4981.6 2103.07  4981.9 2103.57  4997.1 2105.76
  5010.1 2106.04  5031.2 2108.89  5041.7 2111.13  5073.4 2119.94  5085.5 2122.09
  5105.0 2126.13  5115.5 2129.05  5147.2 2134.87  5155.1 2136.83  5157.7 2136.83
#Mann=5,-1,0
  4338.5     0.1       0  4554.8    0.07       0  4977.2    0.05       0
  4981.9    0.07       0  5085.5     0.1       0
Bank Sta=4977.2,4981.9
Exp/Cntr=0.3,0.1

Type RM Length L Ch R = 1,10924,482,482,482
BEGIN DESCRIPTION:
Mullen Creek 24.0
END DESCRIPTION:
XS GIS Cut Line= 3
      1823715.37     13888169.18      1824275.00     13888125.00
      1824375.03     13888125.00
#Sta/Elev= 30
  4438.6 2158.08  4468.3 2152.80  4477.9 2151.99  4548.6 2142.56  4554.4 2140.09
  4559.4 2139.92  4588.7 2133.55  4618.8 2128.78  4648.9 2125.86  4658.9 2123.57
  4668.9 2123.45  4709.1 2119.38  4749.2 2116.99  4779.3 2114.06  4849.5 2109.44
  4859.5 2107.97  4899.7 2104.28  4919.7 2103.33  4929.8 2103.79  4935.6 2102.98
  4940.6 2103.52  4959.9 2100.26  4989.9 2093.72  5007.4 2093.15  5007.8 2092.65
  5012.1 2092.65  5012.5 2093.15  5040.0 2106.85  5060.0 2109.19  5100.0 2111.03
#Mann=4,-1,0
  4438.6     0.1       0  4477.9    0.07       0  5007.4    0.05       0
  5012.5     0.1       0
Bank Sta=5007.4,5012.5
Exp/Cntr=0.3,0.1

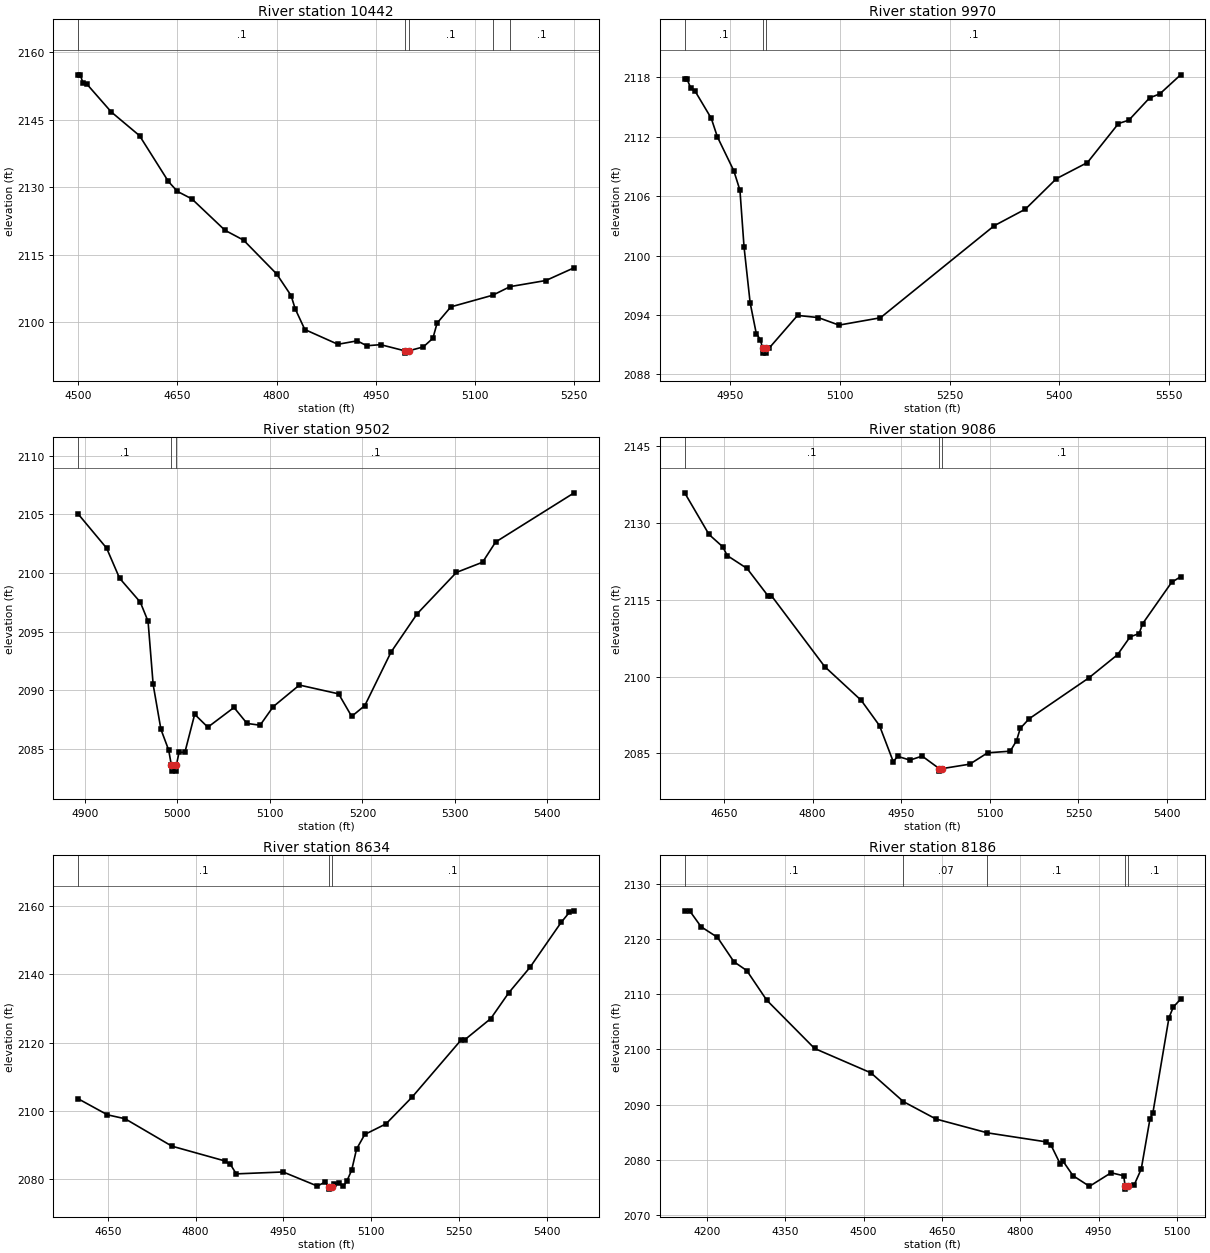
Type RM Length L Ch R = 1,10442,472,472,472
BEGIN DESCRIPTION:
Mullen Creek 23.0
END DESCRIPTION:
XS GIS Cut Line= 3
      1824075.01     13888974.99      1824375.00     13888575.00
      1824525.01     13888374.99
#Sta/Elev= 30
  4500.0 2154.97  4503.1 2154.97  4507.3 2153.12  4513.5 2152.84  4550.0 2146.72
  4592.7 2141.46  4636.4 2131.28  4650.0 2129.08  4671.9 2127.41  4721.9 2120.45
  4750.0 2118.26  4800.0 2110.76  4821.9 2105.95  4828.1 2103.01  4842.7 2098.40
  4892.7 2095.12  4921.9 2095.89  4936.4 2094.80  4957.3 2095.04  4994.2 2093.66
  4994.6 2093.16  4999.5 2093.66  5021.9 2094.54  5036.4 2096.46  5042.7 2099.82
  5063.5 2103.43  5126.8 2106.02  5153.1 2107.93  5207.3 2109.29  5250.0 2112.12
#Mann=5,-1,0
  4500.0     0.1       0  4994.2    0.05       0  4999.5     0.1       0
  5126.8    0.07       0  5153.1     0.1       0
Bank Sta=4994.2,4999.5
Exp/Cntr=0.3,0.1

Type RM Length L Ch R = 1,9970,468,468,468
BEGIN DESCRIPTION:
Mullen Creek 22.0
END DESCRIPTION:
XS GIS Cut Line= 3
      1824374.99     13889025.00      1824475.00     13888975.00
      1824875.00     13888575.00
#Sta/Elev= 30
  4888.2 2117.87  4891.0 2117.87  4896.6 2116.91  4902.2 2116.63  4924.5 2113.86
  4932.9 2111.98  4955.3 2108.56  4963.7 2106.59  4969.3 2100.86  4977.6 2095.24
  4986.0 2092.12  4991.6 2091.50  4994.6 2090.64  4995.0 2090.14  4999.5 2090.14
  4999.9 2090.64  5003.5 2090.64  5042.4 2093.95  5070.7 2093.73  5099.0 2092.97
  5155.6 2093.71  5311.1 2103.01  5353.6 2104.68  5396.0 2107.76  5438.4 2109.39
  5480.8 2113.33  5495.0 2113.67  5523.3 2115.92  5537.4 2116.33  5565.7 2118.25
#Mann=3,-1,0
  4888.2     0.1       0  4994.6    0.05       0  4999.9     0.1       0
Bank Sta=4994.6,4999.9
Exp/Cntr=0.3,0.1

Type RM Length L Ch R = 1,9502,416,416,416
BEGIN DESCRIPTION:
Mullen Creek 21.0
END DESCRIPTION:
XS GIS Cut Line= 3
      1824675.01     13889375.00      1824775.00     13889325.00
      1825075.03     13889024.97
#Sta/Elev= 30
  4892.8 2105.02  4923.5 2102.12  4937.5 2099.56  4959.9 2097.52  4968.3 2095.89
  4973.8 2090.51  4982.2 2086.69  4990.6 2084.92  4993.5 2083.63  4993.9 2083.13
  4998.5 2083.13  4998.9 2083.63  5001.8 2084.73  5008.1 2084.73  5018.7 2087.97
  5032.9 2086.87  5061.2 2088.55  5075.3 2087.19  5089.4 2087.04  5103.6 2088.62
  5131.9 2090.46  5174.3 2089.71  5188.4 2087.79  5202.6 2088.71  5230.9 2093.26
  5259.2 2096.53  5301.6 2100.05  5329.9 2100.92  5344.0 2102.64  5428.9 2106.83
#Mann=3,-1,0
  4892.8     0.1       0  4993.5    0.05       0  4998.9     0.1       0
Bank Sta=4993.5,4998.9
Exp/Cntr=0.3,0.1

Type RM Length L Ch R = 1,9086,452,452,452
BEGIN DESCRIPTION:
Mullen Creek 20.0
END DESCRIPTION:
XS GIS Cut Line= 3
      1824625.04     13889724.99      1825025.00     13889625.00
      1825425.03     13889474.99
#Sta/Elev= 30
  4583.4 2135.82  4624.6 2127.70  4647.8 2125.30  4655.5 2123.58  4689.0 2121.07
  4725.1 2115.64  4730.2 2115.77  4820.4 2101.94  4882.3 2095.35  4913.2 2090.43
  4936.4 2083.42  4944.1 2084.44  4964.7 2083.71  4985.4 2084.49  5014.2 2082.06
  5014.7 2081.56  5019.8 2082.06  5066.0 2082.92  5096.2 2085.13  5134.5 2085.45
  5145.2 2087.50  5151.4 2089.89  5166.5 2091.77  5267.1 2099.70  5316.1 2104.26
  5337.4 2107.74  5352.6 2108.38  5358.8 2110.34  5407.7 2118.37  5422.9 2119.46
#Mann=3,-1,0
  4583.4     0.1       0  5014.2    0.05       0  5019.8     0.1       0
Bank Sta=5014.2,5019.8
Exp/Cntr=0.3,0.1

Type RM Length L Ch R = 1,8634,448,448,448
BEGIN DESCRIPTION:
Mullen Creek 19.0
END DESCRIPTION:
XS GIS Cut Line= 3
      1824874.98     13889925.00      1825275.00     13889925.00
      1825674.97     13889725.02
#Sta/Elev= 30
  4599.5 2103.55  4649.5 2098.86  4679.5 2097.72  4759.5 2089.70  4849.5 2085.40
  4859.5 2084.36  4869.5 2081.59  4949.5 2082.15  5007.9 2078.04  5021.9 2079.25
  5027.5 2077.63  5027.9 2077.13  5033.1 2077.63  5035.9 2078.66  5044.2 2078.92
  5052.6 2077.98  5058.2 2079.42  5066.6 2082.64  5075.0 2088.86  5089.0 2093.12
  5125.3 2096.22  5170.0 2104.07  5253.9 2120.82  5259.5 2120.77  5304.2 2127.00
  5334.9 2134.54  5371.3 2142.01  5424.4 2155.13  5438.4 2158.06  5446.7 2158.53
#Mann=3,-1,0
  4599.5     0.1       0  5027.5    0.05       0  5033.1     0.1       0
Bank Sta=5027.5,5033.1
Exp/Cntr=0.3,0.1

Type RM Length L Ch R = 1,8186,452,452,452
BEGIN DESCRIPTION:
Mullen Creek 18.0
END DESCRIPTION:
XS GIS Cut Line= 3
      1824625.02     13890075.01      1825425.00     13890325.00
      1825524.97     13890275.02
#Sta/Elev= 30
  4157.3 2125.18  4167.8 2125.06  4188.7 2122.29  4220.1 2120.36  4251.6 2115.93
  4276.2 2114.33  4314.4 2108.96  4406.1 2100.18  4514.0 2095.75  4576.3 2090.52
  4638.7 2087.36  4737.3 2084.85  4849.3 2083.22  4859.2 2082.58  4876.5 2079.22
  4881.8 2079.73  4901.1 2077.07  4932.6 2075.14  4974.0 2077.60  4998.2 2077.06
  5001.0 2075.13  5001.5 2074.63  5006.7 2075.13  5017.8 2075.30  5031.8 2078.28
  5048.5 2087.39  5054.1 2088.49  5084.9 2105.78  5093.3 2107.72  5107.2 2109.13
#Mann=5,-1,0
  4157.3     0.1       0  4576.3    0.07       0  4737.3     0.1       0
  5001.0    0.05       0  5006.7     0.1       0
Bank Sta=5001,5006.7
Exp/Cntr=0.3,0.1

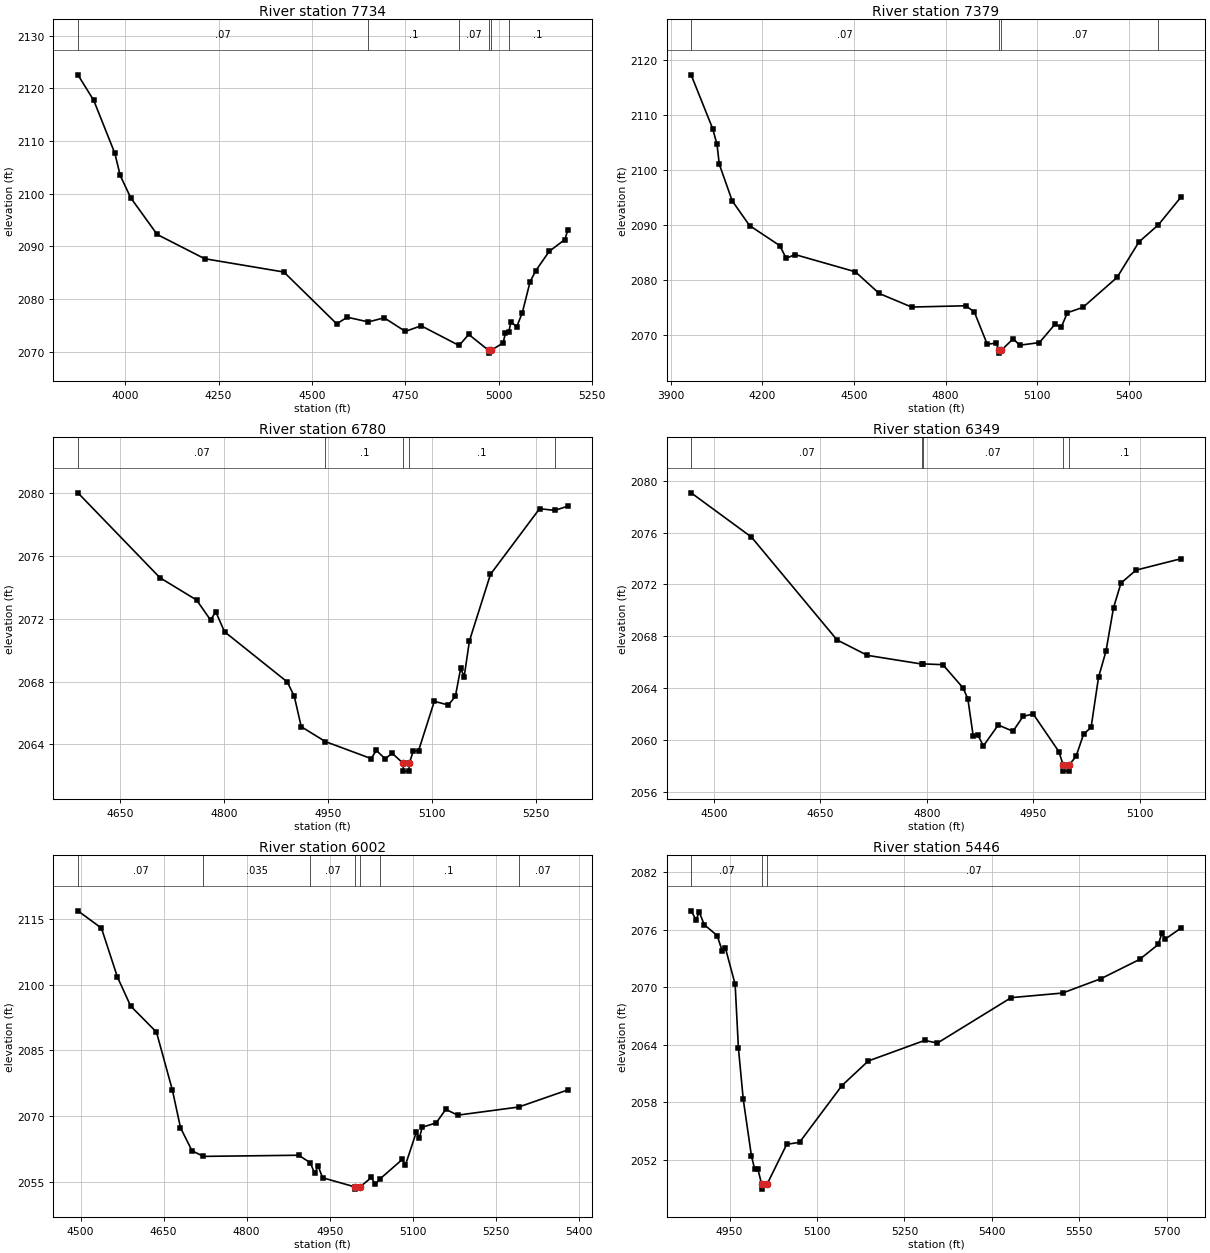
Type RM Length L Ch R = 1,7734,355,355,355
BEGIN DESCRIPTION:
Mullen Creek 17.0
END DESCRIPTION:
XS GIS Cut Line= 4
      1824461.84     13890561.96      1825563.94     13890736.06
      1825575.00     13890725.00      1825675.01     13890574.98
#Sta/Elev= 30
  3873.2 2122.58  3915.7 2117.71  3972.2 2107.65  3986.4 2103.47  4014.7 2099.21
  4085.4 2092.25  4212.6 2087.64  4424.8 2085.11  4566.2 2075.27  4594.5 2076.52
  4651.0 2075.63  4693.5 2076.41  4750.0 2073.83  4792.5 2074.89  4894.1 2071.15
  4919.8 2073.26  4973.5 2070.20  4973.9 2069.70  4979.2 2070.20  5012.1 2071.65
  5018.1 2073.56  5027.1 2073.74  5033.1 2075.68  5048.2 2074.67  5063.2 2077.36
  5084.2 2083.26  5099.3 2085.36  5135.3 2089.03  5177.4 2091.29  5184.9 2093.03
#Mann=6,-1,0
  3873.2    0.07       0  4651.0     0.1       0  4894.1    0.07       0
  4973.5    0.05       0  4979.2    0.07       0  5027.1     0.1       0
Bank Sta=4973.5,4979.2
Exp/Cntr=0.3,0.1

Type RM Length L Ch R = 1,7379,599,599,599
BEGIN DESCRIPTION:
Mullen Creek 16.0
END DESCRIPTION:
XS GIS Cut Line= 4
      1824609.42     13891212.00      1825606.16     13891086.01
      1825659.90     13891035.37      1825756.90     13890519.82
#Sta/Elev= 30
  3967.1 2117.34  4037.7 2107.53  4051.9 2104.66  4059.2 2101.07  4101.7 2094.38
  4158.3 2089.90  4257.0 2086.25  4278.5 2083.92  4306.8 2084.62  4504.6 2081.48
  4582.7 2077.53  4688.7 2075.06  4865.5 2075.29  4893.8 2074.19  4936.3 2068.28
  4964.6 2068.50  4975.6 2067.17  4976.1 2066.67  4982.0 2067.17  5021.3 2069.29
  5042.2 2068.11  5107.0 2068.59  5158.7 2071.97  5178.3 2071.36  5198.6 2074.03
  5249.5 2075.00  5361.4 2080.47  5432.7 2086.91  5496.6 2090.04  5570.2 2095.07
#Mann=4,-1,0
  3967.1    0.07       0  4975.6    0.05       0  4982.0    0.07       0
  5496.6     0.1       0
Bank Sta=4975.6,4982
Exp/Cntr=0.3,0.1

Type RM Length L Ch R = 1,6780,431,431,431
BEGIN DESCRIPTION:
Mullen Creek 15.0
END DESCRIPTION:
XS GIS Cut Line= 3
      1825274.96     13891574.99      1825675.00     13891625.00
      1825975.01     13891575.00
#Sta/Elev= 30
  4588.7 2080.02  4707.2 2074.61  4760.1 2073.19  4780.2 2071.92  4787.8 2072.44
  4800.4 2071.17  4891.1 2067.97  4901.2 2067.05  4911.2 2065.12  4946.2 2064.17
  5012.1 2063.09  5019.7 2063.61  5032.4 2063.07  5042.5 2063.43  5058.3 2062.79
  5058.8 2062.29  5066.8 2062.29  5067.3 2062.79  5073.0 2063.58  5080.6 2063.59
  5103.4 2066.74  5123.6 2066.50  5133.8 2067.06  5141.4 2068.83  5146.5 2068.31
  5154.1 2070.59  5184.5 2074.83  5255.4 2079.01  5277.4 2078.90  5296.0 2079.17
#Mann=5,-1,0
  4588.7    0.07       0  4946.2     0.1       0  5058.3    0.05       0
  5067.3     0.1       0  5277.4    0.07       0
Bank Sta=5058.3,5067.3
Exp/Cntr=0.3,0.1

Type RM Length L Ch R = 1,6349,347,347,347
BEGIN DESCRIPTION:
Mullen Creek 14.0
END DESCRIPTION:
XS GIS Cut Line= 3
      1825274.97     13891674.98      1825675.00     13892025.00
      1825825.04     13891974.99
#Sta/Elev= 30
  4468.0 2079.07  4553.0 2075.65  4673.5 2067.71  4716.2 2066.52  4792.7 2065.85
  4794.8 2065.86  4822.5 2065.80  4851.0 2064.00  4857.7 2063.15  4865.2 2060.29
  4871.9 2060.36  4879.5 2059.52  4900.4 2061.14  4921.2 2060.66  4935.5 2061.81
  4949.7 2061.99  4985.8 2059.09  4991.7 2058.08  4992.2 2057.58  5000.2 2057.58
  5000.7 2058.08  5010.1 2058.73  5020.6 2060.43  5031.2 2060.96  5041.7 2064.83
  5052.2 2066.85  5062.8 2070.20  5073.3 2072.10  5094.4 2073.10  5157.7 2073.98
#Mann=5,-1,0
  4468.0    0.07       0  4792.7   0.035       0  4794.8    0.07       0
  4991.7    0.05       0  5000.7     0.1       0
Bank Sta=4991.7,5000.7
Exp/Cntr=0.3,0.1

Type RM Length L Ch R = 1,6002,556,556,556
BEGIN DESCRIPTION:
Mullen Creek 13.0
END DESCRIPTION:
XS GIS Cut Line= 3
      1825125.03     13892624.98      1825508.55     13892324.25
      1825881.86     13892188.19
#Sta/Elev= 30
  4495.2 2116.80  4537.7 2112.86  4566.6 2101.71  4590.5 2095.11  4637.1 2089.17
  4666.0 2075.89  4680.5 2067.40  4701.3 2062.13  4722.0 2060.86  4893.8 2061.12
  4915.0 2059.41  4922.8 2056.98  4929.1 2058.64  4937.2 2055.99  4995.6 2053.90
  4996.1 2053.40  5004.7 2053.90  5025.4 2056.05  5032.0 2054.47  5040.5 2055.69
  5081.2 2060.17  5086.6 2058.82  5106.5 2066.40  5111.8 2064.99  5117.2 2067.50
  5142.4 2068.50  5159.7 2071.58  5181.0 2070.25  5291.3 2072.10  5379.9 2075.99
#Mann=7,-1,0
  4495.2    0.07       0  4722.0   0.035       0  4915.0    0.07       0
  4995.6    0.05       0  5004.7    0.07       0  5040.5     0.1       0
  5291.3    0.07       0
Bank Sta=4995.6,5004.7
Exp/Cntr=0.3,0.1

Type RM Length L Ch R = 1,5446,424,424,424
BEGIN DESCRIPTION:
Mullen Creek 12.0
END DESCRIPTION:
XS GIS Cut Line= 3
      1825475.00     13892875.00      1825575.00     13892825.00
      1825915.00     13892180.70
#Sta/Elev= 30
  4884.0 2077.96  4892.4 2077.03  4898.0 2077.83  4906.4 2076.52  4928.7 2075.38
  4937.1 2073.82  4942.7 2074.11  4959.5 2070.30  4965.1 2063.68  4973.4 2058.32
  4987.4 2052.44  4993.0 2051.03  4998.6 2051.03  5005.0 2049.45  5005.5 2048.95
  5014.2 2049.45  5048.0 2053.62  5070.0 2053.83  5142.8 2059.75  5188.0 2062.31
  5284.6 2064.45  5306.6 2064.18  5433.1 2068.91  5521.2 2069.39  5587.2 2070.89
  5653.3 2072.89  5685.5 2074.46  5691.7 2075.63  5697.3 2075.01  5724.3 2076.16
#Mann=3,-1,0
  4884.0    0.07       0  5005.0    0.05       0  5014.2    0.07       0
Bank Sta=5005,5014.2
Exp/Cntr=0.3,0.1