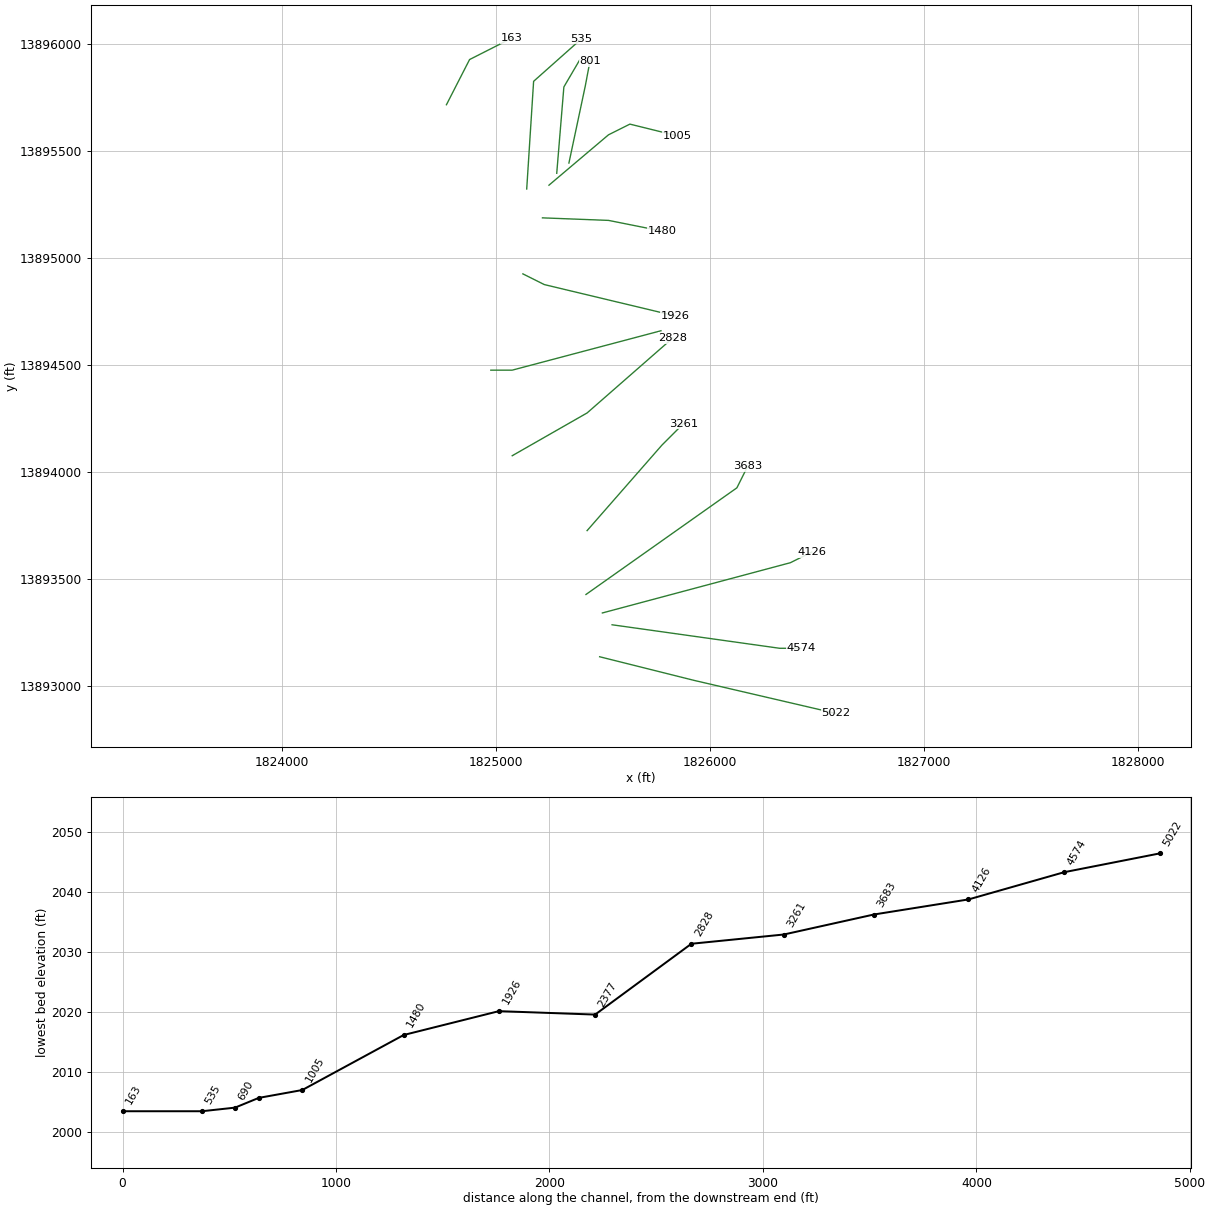
HEC-RAS study Mullen Creek.prj: Mullen Creek Base Level Engineering

--- Mullen Creek.g01 (geometry) --- (continued)

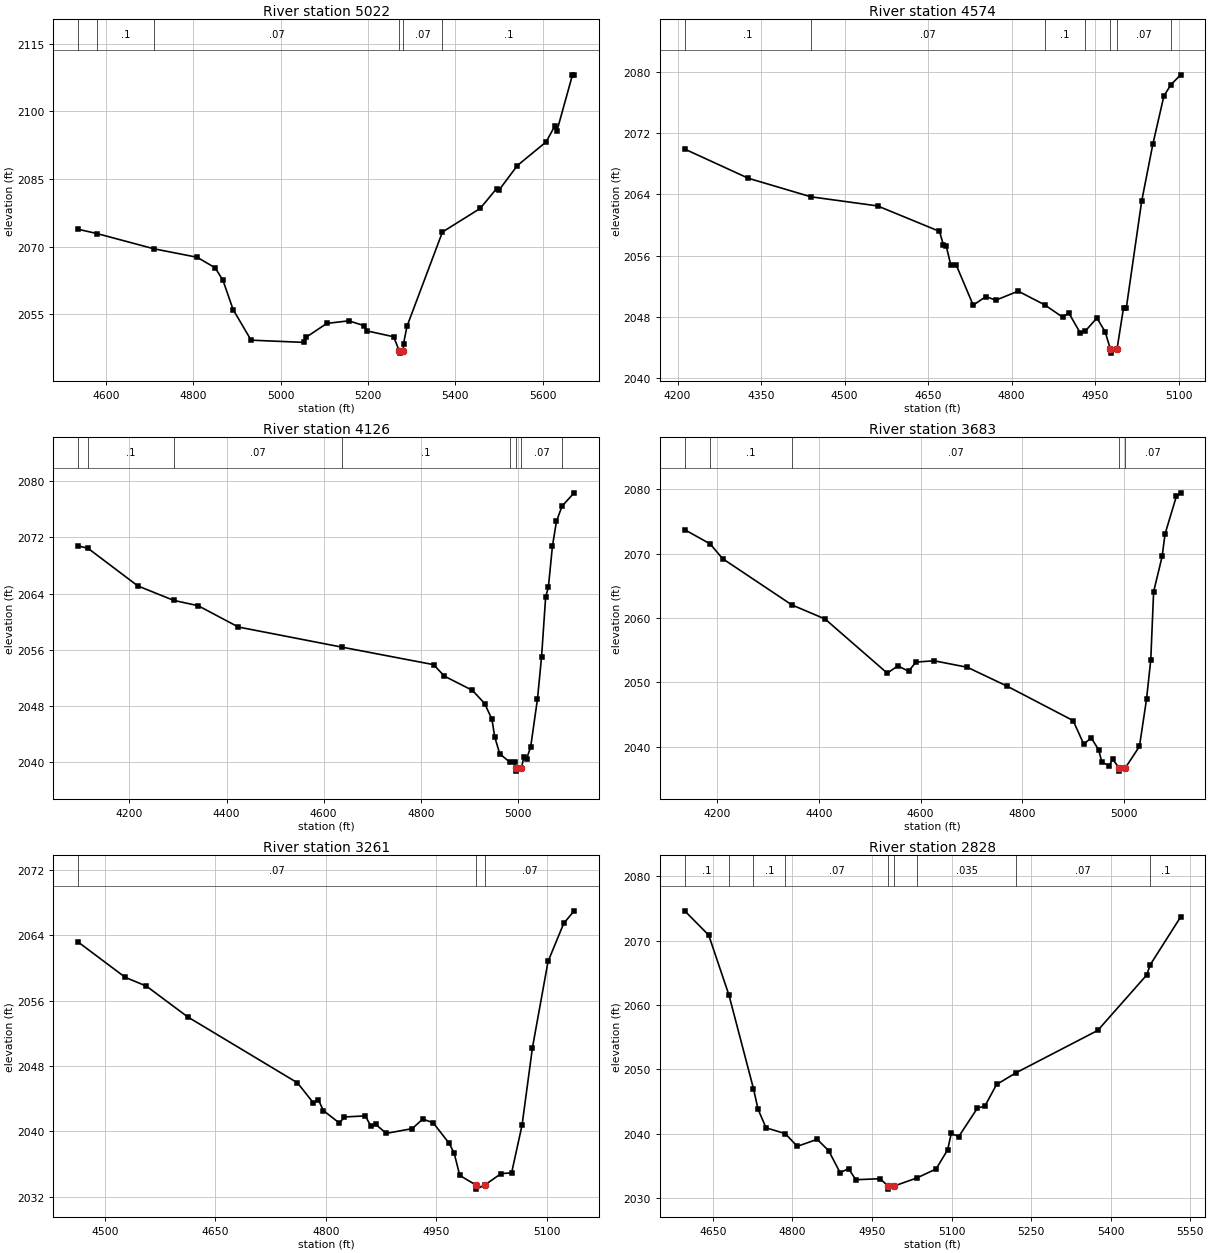
Type RM Length L Ch R = 1,5022,448,448,448
BEGIN DESCRIPTION:
Mullen Creek 11.0
END DESCRIPTION:
XS GIS Cut Line= 3
      1825483.55     13893135.49      1825925.00     13893025.00
      1826587.51     13892870.78
#Sta/Elev= 30
  4536.9 2073.86  4579.7 2072.92  4710.1 2069.54  4809.1 2067.66  4850.3 2065.33
  4868.3 2062.54  4891.5 2056.06  4932.7 2049.28  5053.3 2048.79  5058.4 2049.92
  5106.1 2053.00  5156.3 2053.57  5191.3 2052.50  5197.3 2051.35  5258.9 2050.04
  5271.9 2046.91  5272.4 2046.41  5281.1 2046.91  5281.6 2048.51  5289.7 2052.40
  5370.7 2073.26  5457.1 2078.48  5494.6 2082.87  5499.7 2082.49  5542.3 2088.00
  5608.0 2093.23  5627.5 2096.68  5632.6 2095.60  5668.4 2108.10  5672.2 2108.10
#Mann=6,-1,0
  4536.9    0.07       0  4579.7     0.1       0  4710.1    0.07       0
  5271.9    0.05       0  5281.1    0.07       0  5370.7     0.1       0
Bank Sta=5271.9,5281.1
Exp/Cntr=0.3,0.1

Type RM Length L Ch R = 1,4574,448,448,448
BEGIN DESCRIPTION:
Mullen Creek 10.0
END DESCRIPTION:
XS GIS Cut Line= 3
      1825541.73     13893284.90      1826325.00     13893175.00
      1826424.96     13893175.00
#Sta/Elev= 30
  4212.7 2069.91  4327.1 2066.10  4439.5 2063.68  4559.3 2062.49  4670.4 2059.17
  4677.6 2057.38  4682.7 2057.21  4690.6 2054.82  4700.7 2054.75  4731.0 2049.54
  4754.0 2050.67  4771.4 2050.18  4811.8 2051.37  4859.2 2049.59  4891.6 2047.98
  4902.7 2048.53  4922.9 2045.96  4932.1 2046.13  4953.2 2047.87  4968.0 2046.07
  4977.5 2043.78  4978.0 2043.28  4989.3 2043.78  5001.1 2049.22  5006.1 2049.22
  5033.6 2063.09  5053.6 2070.51  5073.6 2076.86  5086.5 2078.33  5103.6 2079.60
#Mann=7,-1,0
  4212.7     0.1       0  4439.5    0.07       0  4859.2     0.1       0
  4932.1    0.07       0  4977.5    0.05       0  4989.3    0.07       0
  5086.5     0.1       0
Bank Sta=4977.5,4989.3
Exp/Cntr=0.3,0.1

Type RM Length L Ch R = 1,4126,443,443,443
BEGIN DESCRIPTION:
Mullen Creek 9.0
END DESCRIPTION:
XS GIS Cut Line= 3
      1825496.36     13893340.15      1826375.00     13893575.00
      1826475.02     13893625.01
#Sta/Elev= 30
  4094.6 2070.76  4114.4 2070.45  4217.4 2065.08  4291.2 2063.03  4341.6 2062.27
  4424.4 2059.24  4637.6 2056.38  4826.4 2053.89  4848.8 2052.25  4906.5 2050.23
  4931.6 2048.36  4946.6 2046.12  4952.3 2043.62  4962.7 2041.21  4984.1 2039.99
  4993.7 2040.11  4995.5 2039.25  4996.0 2038.75  5007.4 2039.25  5012.5 2040.80
  5018.1 2040.52  5026.4 2042.21  5040.4 2049.02  5048.8 2055.01  5057.2 2063.52
  5062.8 2064.90  5071.2 2070.75  5079.5 2074.28  5091.0 2076.43  5115.9 2078.32
#Mann=8,-1,0
  4094.6    0.07       0  4114.4     0.1       0  4291.2    0.07       0
  4637.6     0.1       0  4984.1    0.07       0  4995.5    0.05       0
  5007.4    0.07       0  5091.0     0.1       0
Bank Sta=4995.5,5007.4
Exp/Cntr=0.3,0.1

Type RM Length L Ch R = 1,3683,422,422,422
BEGIN DESCRIPTION:
Mullen Creek 8.0
END DESCRIPTION:
XS GIS Cut Line= 3
      1825419.58     13893426.42      1826125.00     13893925.00
      1826174.99     13894024.97
#Sta/Elev= 30
  4135.9 2073.70  4185.9 2071.50  4210.6 2069.20  4346.7 2062.03  4411.9 2059.85
  4534.4 2051.44  4555.3 2052.57  4576.2 2051.74  4591.0 2053.16  4626.7 2053.36
  4692.0 2052.35  4769.5 2049.45  4900.0 2044.08  4920.9 2040.44  4935.7 2041.39
  4950.5 2039.51  4956.6 2037.60  4971.4 2037.10  4977.5 2038.09  4990.7 2036.74
  4991.2 2036.24  5002.7 2036.74  5030.5 2040.07  5044.4 2047.37  5052.8 2053.53
  5058.4 2064.08  5075.2 2069.57  5080.8 2073.02  5103.1 2078.86  5111.5 2079.42
#Mann=5,-1,0
  4135.9    0.07       0  4185.9     0.1       0  4346.7    0.07       0
  4990.7    0.05       0  5002.7    0.07       0
Bank Sta=4990.7,5002.7
Exp/Cntr=0.3,0.1

Type RM Length L Ch R = 1,3261,433,433,433
BEGIN DESCRIPTION:
Mullen Creek 7.0
END DESCRIPTION:
XS GIS Cut Line= 3
      1825425.03     13893725.03      1825775.00     13894125.00
      1825875.01     13894225.01
#Sta/Elev= 30
  4463.9 2063.17  4527.9 2058.84  4556.4 2057.78  4612.4 2054.01  4761.4 2045.93
  4782.8 2043.49  4789.9 2043.82  4796.5 2042.54  4818.4 2040.99  4825.0 2041.75
  4853.5 2041.88  4861.1 2040.60  4867.7 2040.83  4881.9 2039.74  4917.1 2040.32
  4931.3 2041.49  4945.5 2041.04  4967.4 2038.50  4974.0 2037.31  4981.6 2034.59
  5003.5 2033.41  5004.0 2032.91  5015.5 2033.41  5037.8 2034.82  5051.9 2034.89
  5066.1 2040.74  5080.2 2050.23  5101.4 2060.80  5122.6 2065.45  5136.8 2067.00
#Mann=3,-1,0
  4463.9    0.07       0  5003.5    0.05       0  5015.5    0.07       0
Bank Sta=5003.5,5015.5
Exp/Cntr=0.3,0.1

Type RM Length L Ch R = 1,2828,451,451,451
BEGIN DESCRIPTION:
Mullen Creek 6.0
END DESCRIPTION:
XS GIS Cut Line= 3
      1825075.03     13894075.02      1825425.00     13894275.00
      1825825.01     13894625.01
#Sta/Elev= 30
  4597.0 2074.62  4642.3 2070.84  4680.5 2061.51  4726.6 2047.00  4735.2 2043.80
  4750.3 2040.90  4786.4 2040.00  4809.3 2038.02  4846.7 2039.11  4868.3 2037.35
  4889.9 2033.93  4905.8 2034.56  4919.5 2032.83  4964.8 2032.99  4980.3 2031.87
  4980.8 2031.37  4992.4 2031.87  5034.9 2033.12  5070.8 2034.50  5092.6 2037.49
  5099.3 2040.02  5113.5 2039.54  5148.6 2043.95  5162.8 2044.28  5184.7 2047.63
  5221.9 2049.47  5375.5 2056.04  5467.5 2064.63  5474.5 2066.26  5531.6 2073.66
#Mann=9,-1,0
  4597.0     0.1       0  4680.5    0.07       0  4726.6     0.1       0
  4786.4    0.07       0  4980.3    0.05       0  4992.4    0.07       0
  5034.9   0.035       0  5221.9    0.07       0  5474.5     0.1       0
Bank Sta=4980.3,4992.4
Exp/Cntr=0.3,0.1

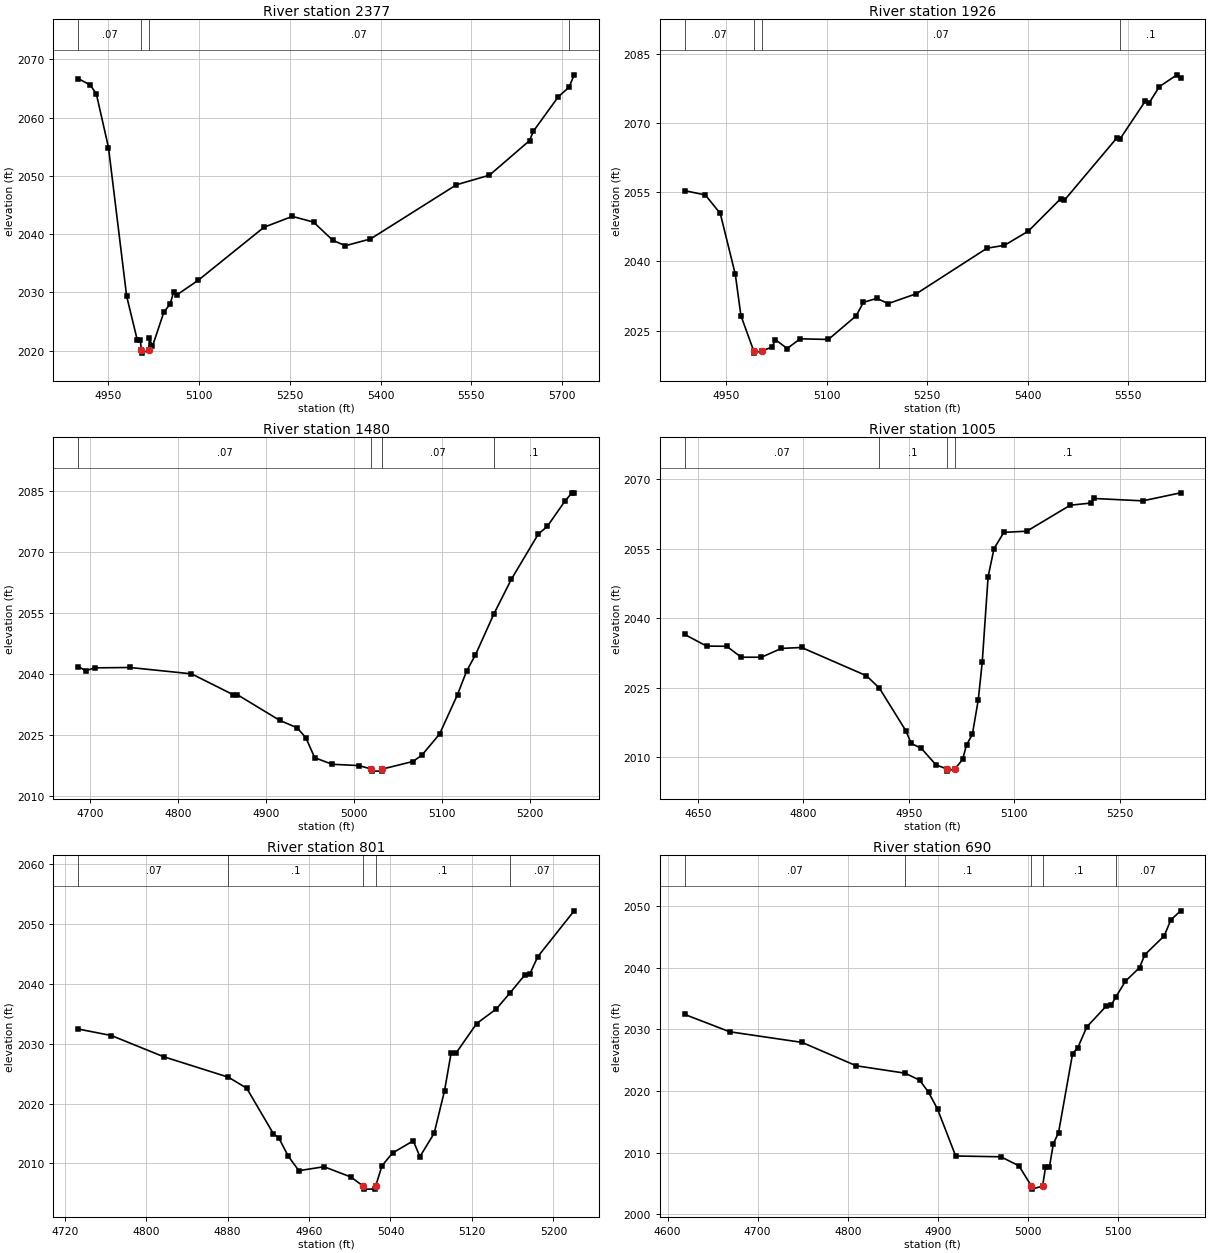
Type RM Length L Ch R = 1,2377,451,451,451
BEGIN DESCRIPTION:
Mullen Creek 5.0
END DESCRIPTION:
XS GIS Cut Line= 3
      1824975.00     13894475.00      1825075.00     13894475.00
      1825770.22     13894659.16
#Sta/Elev= 30
  4900.5 2066.68  4920.5 2065.58  4930.5 2064.03  4950.5 2054.86  4980.5 2029.35
  4998.0 2021.85  5003.1 2021.85  5004.8 2020.08  5005.3 2019.58  5016.9 2020.08
  5018.0 2022.09  5023.2 2020.77  5041.9 2026.59  5052.2 2027.99  5058.2 2030.07
  5063.4 2029.57  5098.5 2032.06  5207.4 2041.18  5254.1 2043.04  5289.2 2042.06
  5321.2 2038.92  5341.9 2038.01  5383.3 2039.17  5525.3 2048.47  5579.8 2050.11
  5646.0 2056.04  5652.2 2057.63  5693.6 2063.58  5711.3 2065.20  5719.7 2067.33
#Mann=4,-1,0
  4900.5    0.07       0  5004.8    0.05       0  5016.9    0.07       0
  5711.3     0.1       0
Bank Sta=5004.8,5016.9
Exp/Cntr=0.3,0.1

Type RM Length L Ch R = 1,1926,446,446,446
BEGIN DESCRIPTION:
Mullen Creek 4.0
END DESCRIPTION:
XS GIS Cut Line= 3
      1825124.98     13894925.01      1825225.00     13894875.00
      1825835.85     13894728.89
#Sta/Elev= 30
  4888.4 2055.34  4919.2 2054.40  4941.5 2050.40  4963.9 2037.24  4972.3 2028.28
  4991.3 2020.65  4991.8 2020.15  5003.5 2020.65  5018.7 2021.44  5023.8 2023.06
  5041.3 2021.15  5060.7 2023.25  5102.8 2023.11  5144.2 2028.23  5155.1 2031.16
  5175.0 2032.00  5192.0 2030.88  5234.1 2033.02  5339.5 2042.88  5365.4 2043.49
  5401.2 2046.58  5449.5 2053.61  5454.7 2053.23  5533.6 2066.83  5537.7 2066.49
  5575.7 2074.75  5580.8 2074.22  5596.6 2077.86  5622.9 2080.42  5628.3 2079.84
#Mann=4,-1,0
  4888.4    0.07       0  4991.3    0.05       0  5003.5    0.07       0
  5537.7     0.1       0
Bank Sta=4991.3,5003.5
Exp/Cntr=0.3,0.1

Type RM Length L Ch R = 1,1480,475,475,475
BEGIN DESCRIPTION:
Mullen Creek 3.0
END DESCRIPTION:
XS GIS Cut Line= 3
      1825216.27     13895186.84      1825525.00     13895175.00
      1825775.00     13895125.00
#Sta/Elev= 30
  4686.6 2041.89  4695.3 2040.88  4705.3 2041.58  4745.4 2041.67  4815.4 2040.11
  4862.7 2034.99  4867.7 2034.96  4915.5 2028.69  4935.5 2026.84  4945.5 2024.37
  4955.5 2019.47  4975.5 2017.86  5005.7 2017.55  5020.0 2016.68  5020.5 2016.18
  5031.7 2016.18  5032.2 2016.68  5066.9 2018.54  5077.1 2020.03  5097.5 2025.31
  5117.9 2035.01  5128.1 2040.72  5138.3 2044.79  5159.3 2054.88  5179.1 2063.37
  5209.7 2074.48  5219.9 2076.36  5240.3 2082.67  5248.0 2084.63  5250.5 2084.63
#Mann=4,-1,0
  4686.6    0.07       0  5020.0    0.05       0  5032.2    0.07       0
  5159.3     0.1       0
Bank Sta=5020,5032.2
Exp/Cntr=0.3,0.1

Type RM Length L Ch R = 1,1005,204,204,204
BEGIN DESCRIPTION:
Mullen Creek 2.0
END DESCRIPTION:
XS GIS Cut Line= 4
      1825246.70     13895339.57      1825525.00     13895575.00
      1825625.00     13895625.00      1825847.36     13895569.96
#Sta/Elev= 30
  4631.1 2036.48  4662.2 2033.97  4690.8 2033.93  4711.6 2031.57  4740.2 2031.57
  4768.8 2033.47  4797.3 2033.67  4889.6 2027.58  4908.0 2024.92  4945.6 2015.74
  4953.4 2012.98  4967.6 2011.94  4988.5 2008.38  5003.5 2007.52  5004.0 2007.02
  5015.7 2007.52  5026.4 2009.54  5032.0 2012.67  5040.3 2014.95  5048.7 2022.39
  5054.3 2030.47  5062.7 2048.94  5071.1 2054.98  5085.1 2058.48  5117.7 2058.73
  5179.5 2064.33  5208.4 2064.79  5213.5 2065.78  5282.6 2065.27  5336.5 2067.00
#Mann=4,-1,0
  4631.1    0.07       0  4908.0     0.1       0  5003.5    0.05       0
  5015.7     0.1       0
Bank Sta=5003.5,5015.7
Exp/Cntr=0.3,0.1

Type RM Length L Ch R = 1,801,111,111,111
BEGIN DESCRIPTION:
Mullen Creek 1.2
END DESCRIPTION:
XS GIS Cut Line= 3
      1825340.00     13895443.07      1825416.40     13895802.82
      1825438.60     13895920.07
#Sta/Elev= 30
  4733.3 2032.45  4765.9 2031.36  4817.1 2027.83  4880.9 2024.40  4898.8 2022.56
  4925.1 2014.94  4930.2 2014.29  4939.7 2011.19  4950.0 2008.79  4974.7 2009.45
  5001.1 2007.74  5013.2 2006.21  5013.7 2005.71  5024.9 2005.71  5025.4 2006.21
  5031.7 2009.62  5042.0 2011.74  5062.4 2013.78  5068.9 2011.13  5082.9 2015.04
  5093.1 2022.15  5099.6 2028.50  5104.7 2028.50  5124.6 2033.36  5144.0 2035.81
  5157.6 2038.52  5171.8 2041.45  5176.9 2041.66  5184.7 2044.54  5220.4 2052.19
#Mann=5,-1,0
  4733.3    0.07       0  4880.9     0.1       0  5013.2    0.05       0
  5025.4     0.1       0  5157.6    0.07       0
Bank Sta=5013.2,5025.4
Exp/Cntr=0.3,0.1

Type RM Length L Ch R = 1,690,155,155,155
BEGIN DESCRIPTION:
Mullen Creek 1.1
END DESCRIPTION:
XS GIS Cut Line= 3
      1825283.07     13895395.21      1825316.40     13895798.65
      1825390.02     13895924.37
#Sta/Elev= 30
  4619.0 2032.40  4669.0 2029.59  4749.2 2027.87  4809.4 2024.08  4863.6 2022.88
  4879.7 2021.76  4889.7 2019.79  4899.7 2017.05  4919.8 2009.46  4970.0 2009.33
  4990.0 2007.87  5003.9 2004.59  5004.4 2004.09  5016.3 2004.59  5019.5 2007.60
  5023.8 2007.60  5028.2 2011.44  5034.0 2013.25  5049.6 2026.06  5055.4 2027.01
  5065.3 2030.37  5086.8 2033.73  5092.6 2033.94  5097.5 2035.21  5108.3 2037.79
  5123.9 2039.99  5129.8 2042.08  5151.3 2045.13  5158.6 2047.71  5169.5 2049.19
#Mann=5,-1,0
  4619.0    0.07       0  4863.6     0.1       0  5003.9    0.05       0
  5016.3     0.1       0  5097.5    0.07       0
Bank Sta=5003.9,5016.3
Exp/Cntr=0.3,0.1

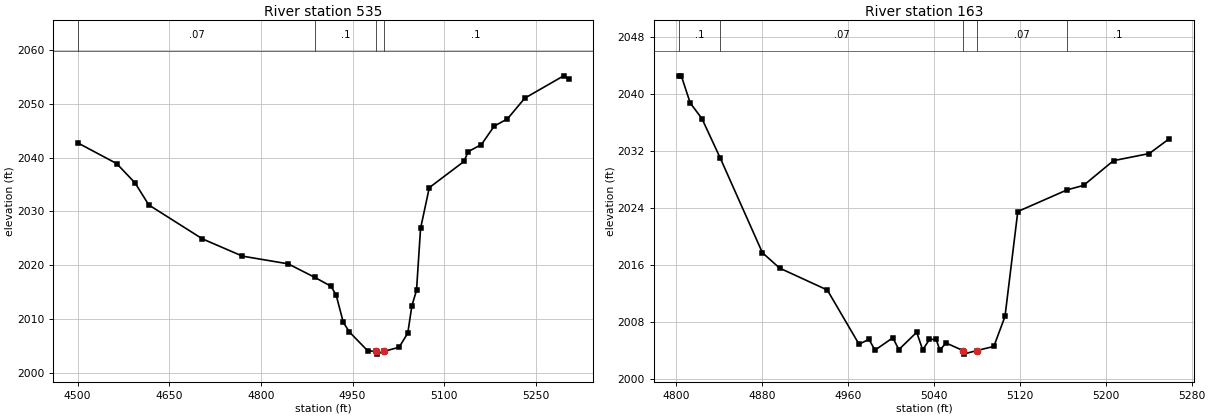
Type RM Length L Ch R = 1,535,372,372,372
BEGIN DESCRIPTION:
Mullen Creek 1.0
END DESCRIPTION:
XS GIS Cut Line= 3
      1825142.76     13895321.73      1825175.00     13895825.00
      1825398.20     13896023.50
#Sta/Elev= 30
  4500.6 2042.73  4564.0 2038.90  4594.1 2035.30  4616.5 2031.22  4704.3 2024.91
  4769.8 2021.70  4844.6 2020.27  4888.1 2017.76  4914.7 2016.11  4923.2 2014.46
  4934.8 2009.41  4944.8 2007.61  4974.8 2004.11  4988.7 2003.99  4989.2 2003.49
  5001.1 2003.99  5026.2 2004.77  5040.4 2007.40  5047.1 2012.48  5054.7 2015.35
  5061.3 2026.85  5075.6 2034.43  5132.4 2039.30  5139.1 2041.11  5160.9 2042.44
  5181.8 2045.86  5203.5 2047.21  5231.9 2051.06  5295.5 2055.21  5303.6 2054.66
#Mann=4,-1,0
  4500.6    0.07       0  4888.1     0.1       0  4988.7    0.05       0
  5001.1     0.1       0
Bank Sta=4988.7,5001.1
Exp/Cntr=0.3,0.1

Type RM Length L Ch R = 1,163,0,0,0
BEGIN DESCRIPTION:
Mullen Creek 0.0
END DESCRIPTION:
XS GIS Cut Line= 3
      1824767.58     13895715.57      1824875.72     13895926.80
      1825071.44     13896025.94
#Sta/Elev= 30
  4802.4 2042.60  4804.9 2042.60  4813.2 2038.78  4824.1 2036.59  4841.1 2031.06
  4880.4 2017.74  4896.4 2015.58  4940.8 2012.50  4970.3 2004.89  4979.6 2005.56
  4985.2 2004.05  5001.8 2005.79  5007.4 2004.13  5024.0 2006.56  5029.6 2004.09
  5035.9 2005.56  5042.1 2005.56  5045.6 2004.06  5051.3 2005.06  5067.1 2003.99
  5067.6 2003.49  5079.9 2003.99  5095.8 2004.57  5106.2 2008.79  5118.1 2023.53
  5164.1 2026.58  5179.3 2027.20  5207.2 2030.68  5240.5 2031.68  5259.1 2033.76
#Mann=5,-1,0
  4802.4     0.1       0  4841.1    0.07       0  5067.1    0.05       0
  5079.9    0.07       0  5164.1     0.1       0
Bank Sta=5067.1,5079.9
Exp/Cntr=0.3,0.1

Chan Stop Cuts=-1