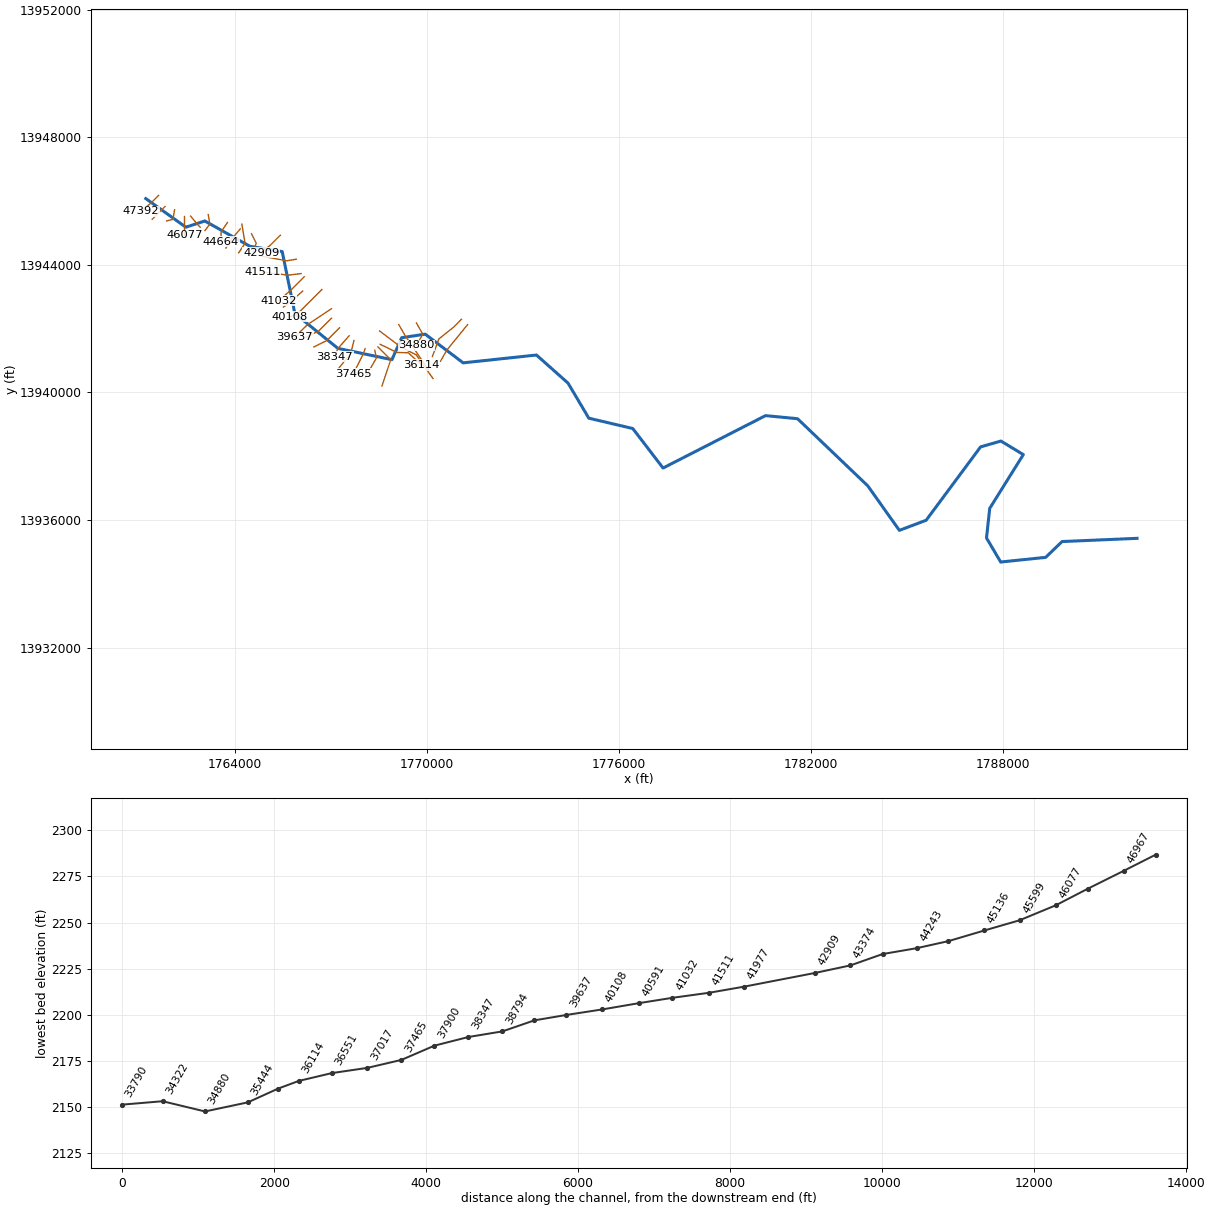
--- North Fork Guadalupe River.prj (project) ---

Proj Title=North Fork Guadalupe River Base Level Engineering
Current Plan=p01
Default Exp/Contr=0.3,0.1
English Units
Geom File=g01
Flow File=f01
Plan File=p01
BEGIN DESCRIPTION:
North Fork Guadalupe River
END DESCRIPTION:

--- North Fork Guadalupe River.p01 (plan) ---

Plan Title=Multiple Run
Short Identifier=Multiple
Geom File=g01
Flow File=f01
Subcritical Flow
K Sum by GR= 0
Std Step Tol= 0.01
Critical Tol= 0.01
Num of Std Step Trials= 20
Max Error Tol= 0.3
Flow Tol Ratio= 0.001
Split Flow NTrial= 30
Split Flow Tol= 0.02
Split Flow Ratio= 0.02
Log Output Level= 0
Friction Slope Method= 1
Unsteady Friction Slope Method= 2
Unsteady Bridges Friction Slope Method= 1
Parabolic Critical Depth
Global Vel Dist=  1 , 1 , 1
Global Log Level= 0
CheckData=True
Encroach Param= -1, 0, 0, 0
BEGIN DESCRIPTION:
Multiple Run
END DESCRIPTION:

--- North Fork Guadalupe River.f01 (steady flow) ---

Flow Title=Multiple
Number of Profiles=7
Profile Names=10-year,25-year,50-year,1pct_min,100-year,1pct_plu,500-year
River Rch & RM= North Fork Guada,Reach-1,47392
     497     814    1104     725    1447    2887    2453
River Rch & RM= North Fork Guada,Reach-1,45599
    1060    1819    2542    1715    3423    6829    6140
River Rch & RM= North Fork Guada,Reach-1,41977
    1479    2577    3638    2476    4940    9857    9022
River Rch & RM= North Fork Guada,Reach-1,36114
    4987    9049   13126    9139   18235   36383   34854
River Rch & RM= North Fork Guada,Reach-1,34322
    5598   10195   14823   10341   20633   41169   39599
River Rch & RM= North Fork Guada,Reach-1,29554
    5723   10414   15134   10551   21051   42003   40344
River Rch & RM= North Fork Guada,Reach-1,26674
    5729   10411   15116   10528   21005   41911   40176
River Rch & RM= North Fork Guada,Reach-1,21209
    6580   12015   17503   12226   24395   48674   46935
River Rch & RM= North Fork Guada,Reach-1,20915
    7041   12885   18798   13149   26235   52346   50608
River Rch & RM= North Fork Guada,Reach-1,19491
    7168   13124   19154   13402   26740   53353   51612
River Rch & RM= North Fork Guada,Reach-1,15608
    7477   13715   20039   14038   28009   55886   54188
River Rch & RM= North Fork Guada,Reach-1,15041
    7548   13829   20191   14132   28198   56262   54458
River Rch & RM= North Fork Guada,Reach-1,9793
    8722   16038   23476   16467   32857   65558   63728
Boundary for River Rch & Prof#=North Fork Guada,Reach-1,1
Up Type=0
Dn Type=3
Dn Slope=0.005
Boundary for River Rch & Prof#=North Fork Guada,Reach-1,2
Up Type=0
Dn Type=3
Dn Slope=0.005
Boundary for River Rch & Prof#=North Fork Guada,Reach-1,3
Up Type=0
Dn Type=3
Dn Slope=0.005
Boundary for River Rch & Prof#=North Fork Guada,Reach-1,4
Up Type=0
Dn Type=3
Dn Slope=0.005
Boundary for River Rch & Prof#=North Fork Guada,Reach-1,5
Up Type=0
Dn Type=3
Dn Slope=0.005
Boundary for River Rch & Prof#=North Fork Guada,Reach-1,6
Up Type=0
Dn Type=3
Dn Slope=0.005
Boundary for River Rch & Prof#=North Fork Guada,Reach-1,7
Up Type=0
Dn Type=3
Dn Slope=0.005

--- North Fork Guadalupe River.g01 (geometry) ---

Geom Title=Existing Conditions

River Reach=North Fork Guada,Reach-1
Reach XY= 30
      1761225.00     13946075.00      1762476.58     13945178.67
      1763069.30     13945373.09      1764476.50     13944578.47
      1765484.81     13944414.58      1765880.42     13942472.33
      1767222.58     13941380.54      1768911.08     13941025.68
      1769215.29     13941714.25      1769950.08     13941825.20
      1771135.50     13940926.20      1773423.45     13941171.25
      1774408.76     13940292.04      1775058.29     13939191.64
      1776431.19     13938867.19      1777376.46     13937628.54
      1780576.47     13939271.45      1781575.00     13939175.00
      1783769.38     13937069.38      1784754.79     13935674.64
      1785591.67     13935991.65      1787291.43     13938291.76
      1787925.00     13938475.00      1788625.51     13938050.04
      1787576.20     13936364.50      1787476.19     13935435.50
      1787918.81     13934682.81      1789323.99     13934828.61
      1789835.48     13935324.07      1792175.00     13935425.00

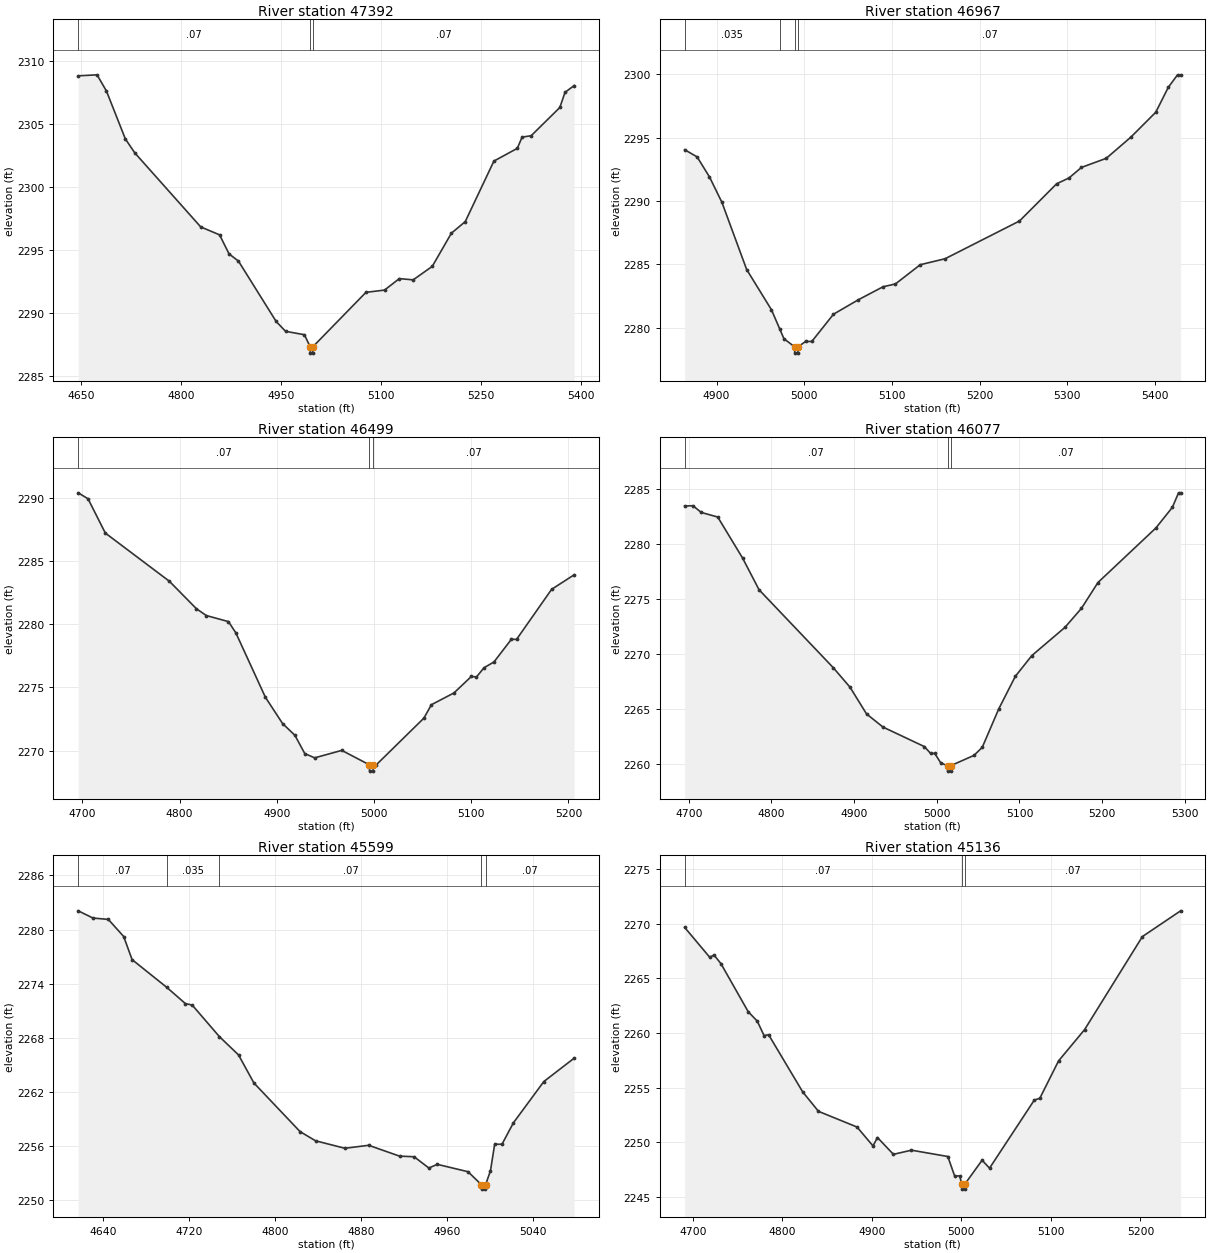
Type RM Length L Ch R = 1,47392,425,425,425
BEGIN DESCRIPTION:
North Fork Guadalupe River 88.0
END DESCRIPTION:
XS GIS Cut Line= 3
      1761625.00     13946175.00      1761375.00     13945925.00
      1761074.97     13945674.98
#Sta/Elev= 30
  4646.2 2308.83  4674.5 2308.91  4688.6 2307.62  4716.9 2303.83  4731.1 2302.72
  4830.0 2296.85  4858.3 2296.22  4872.5 2294.71  4886.6 2294.14  4943.2 2289.35
  4957.3 2288.57  4985.6 2288.30  4994.2 2287.34  4994.5 2286.84  4998.0 2286.84
  4998.2 2287.34  5077.9 2291.66  5105.8 2291.84  5128.0 2292.75  5148.8 2292.65
  5177.4 2293.72  5206.1 2296.35  5226.9 2297.27  5269.9 2302.07  5305.0 2303.08
  5312.2 2303.97  5325.8 2304.08  5368.8 2306.32  5376.6 2307.52  5390.3 2308.06
#Mann=3,-1,0
  4646.2    0.07       0  4994.2    0.05       0  4998.2    0.07       0
Bank Sta=4994.2,4998.2
Exp/Cntr=0.3,0.1

Type RM Length L Ch R = 1,46967,468,468,468
BEGIN DESCRIPTION:
North Fork Guadalupe River 87.0
END DESCRIPTION:
XS GIS Cut Line= 3
      1761825.02     13945825.02      1761725.00     13945725.00
      1761425.01     13945425.01
#Sta/Elev= 30
  4863.6 2294.04  4877.8 2293.47  4891.9 2291.89  4906.1 2289.88  4934.3 2284.58
  4962.6 2281.40  4971.9 2279.91  4976.8 2279.12  4988.9 2278.48  4989.2 2277.98
  4992.7 2277.98  4992.9 2278.48  5001.5 2278.90  5008.6 2278.90  5033.3 2281.05
  5061.6 2282.19  5089.9 2283.22  5104.0 2283.44  5132.3 2284.96  5160.6 2285.43
  5245.5 2288.41  5287.9 2291.35  5302.0 2291.81  5316.2 2292.64  5344.5 2293.36
  5372.7 2295.04  5401.0 2297.00  5415.2 2298.96  5425.8 2299.95  5429.3 2299.95
#Mann=4,-1,0
  4863.6   0.035       0  4971.9    0.07       0  4988.9    0.05       0
  4992.9    0.07       0
Bank Sta=4988.9,4992.9
Exp/Cntr=0.3,0.1

Type RM Length L Ch R = 1,46499,422,422,422
BEGIN DESCRIPTION:
North Fork Guadalupe River 86.0
END DESCRIPTION:
XS GIS Cut Line= 3
      1762125.00     13945724.98      1762075.00     13945425.00
      1761874.97     13945374.99
#Sta/Elev= 30
  4695.6 2290.38  4705.7 2289.91  4723.5 2287.20  4789.4 2283.39  4817.2 2281.22
  4827.4 2280.68  4850.2 2280.20  4857.8 2279.31  4888.2 2274.22  4905.9 2272.14
  4918.6 2271.21  4928.7 2269.77  4938.9 2269.43  4966.8 2270.02  4995.2 2268.88
  4995.4 2268.38  4998.9 2268.38  4999.2 2268.88  5002.3 2268.88  5051.3 2272.57
  5059.0 2273.63  5082.2 2274.56  5100.2 2275.87  5105.4 2275.82  5113.1 2276.55
  5123.4 2277.01  5141.4 2278.81  5146.6 2278.79  5182.7 2282.75  5205.9 2283.90
#Mann=3,-1,0
  4695.6    0.07       0  4995.2    0.05       0  4999.2    0.07       0
Bank Sta=4995.2,4999.2
Exp/Cntr=0.3,0.1

Type RM Length L Ch R = 1,46077,478,478,478
BEGIN DESCRIPTION:
North Fork Guadalupe River 85.0
END DESCRIPTION:
XS GIS Cut Line= 3
      1762425.00     13945524.95      1762425.00     13945225.00
      1762425.00     13944924.95
#Sta/Elev= 30
  4695.0 2283.46  4705.0 2283.49  4715.0 2282.88  4735.0 2282.46  4765.0 2278.74
  4785.0 2275.85  4875.0 2268.75  4895.0 2267.00  4915.0 2264.57  4935.0 2263.37
  4985.0 2261.60  4992.5 2260.98  4997.5 2260.98  5005.0 2260.10  5013.0 2259.87
  5013.2 2259.37  5016.7 2259.37  5017.0 2259.87  5045.0 2260.80  5055.0 2261.53
  5075.0 2265.03  5095.0 2267.98  5115.0 2269.87  5155.0 2272.43  5175.0 2274.16
  5195.0 2276.51  5265.0 2281.46  5285.0 2283.34  5292.5 2284.66  5295.0 2284.66
#Mann=3,-1,0
  4695.0    0.07       0  5013.0    0.05       0  5017.0    0.07       0
Bank Sta=5013,5017
Exp/Cntr=0.3,0.1

Type RM Length L Ch R = 1,45599,463,463,463
BEGIN DESCRIPTION:
North Fork Guadalupe River 84.0
END DESCRIPTION:
XS GIS Cut Line= 3
      1762624.99     13945525.01      1762875.00     13945225.00
      1762924.97     13945175.03
#Sta/Elev= 30
  4617.2 2282.08  4630.9 2281.28  4645.2 2281.13  4659.5 2279.23  4667.3 2276.67
  4699.6 2273.59  4716.8 2271.80  4723.3 2271.62  4748.5 2268.13  4766.3 2266.10
  4780.6 2262.99  4823.5 2257.60  4837.9 2256.58  4865.2 2255.75  4887.3 2256.08
  4916.0 2254.88  4929.6 2254.81  4943.3 2253.56  4951.1 2253.97  4979.7 2253.15
  4992.1 2251.72  4992.3 2251.22  4995.8 2251.22  4996.1 2251.72  5000.6 2253.27
  5004.5 2256.20  5011.3 2256.20  5021.9 2258.57  5050.2 2263.15  5078.4 2265.74
#Mann=5,-1,0
  4617.2    0.07       0  4699.6   0.035       0  4748.5    0.07       0
  4992.1    0.05       0  4996.1    0.07       0
Bank Sta=4992.1,4996.1
Exp/Cntr=0.3,0.1

Type RM Length L Ch R = 1,45136,472,472,472
BEGIN DESCRIPTION:
North Fork Guadalupe River 83.0
END DESCRIPTION:
XS GIS Cut Line= 3
      1763175.00     13945574.99      1763225.00     13945275.00
      1763075.02     13945075.02
#Sta/Elev= 30
  4690.8 2269.68  4718.7 2266.95  4723.7 2267.14  4731.3 2266.36  4761.8 2261.95
  4771.9 2261.09  4779.5 2259.76  4784.6 2259.84  4822.6 2254.61  4840.3 2252.82
  4883.4 2251.38  4901.2 2249.65  4906.2 2250.42  4924.0 2248.88  4944.2 2249.26
  4984.8 2248.68  4992.4 2246.90  4998.1 2246.90  5000.2 2246.19  5000.5 2245.69
  5004.0 2245.69  5004.2 2246.19  5023.1 2248.34  5031.4 2247.61  5081.4 2253.85
  5087.6 2254.02  5108.5 2257.44  5137.6 2260.31  5202.2 2268.84  5244.9 2271.20
#Mann=3,-1,0
  4690.8    0.07       0  5000.2    0.05       0  5004.2    0.07       0
Bank Sta=5000.2,5004.2
Exp/Cntr=0.3,0.1

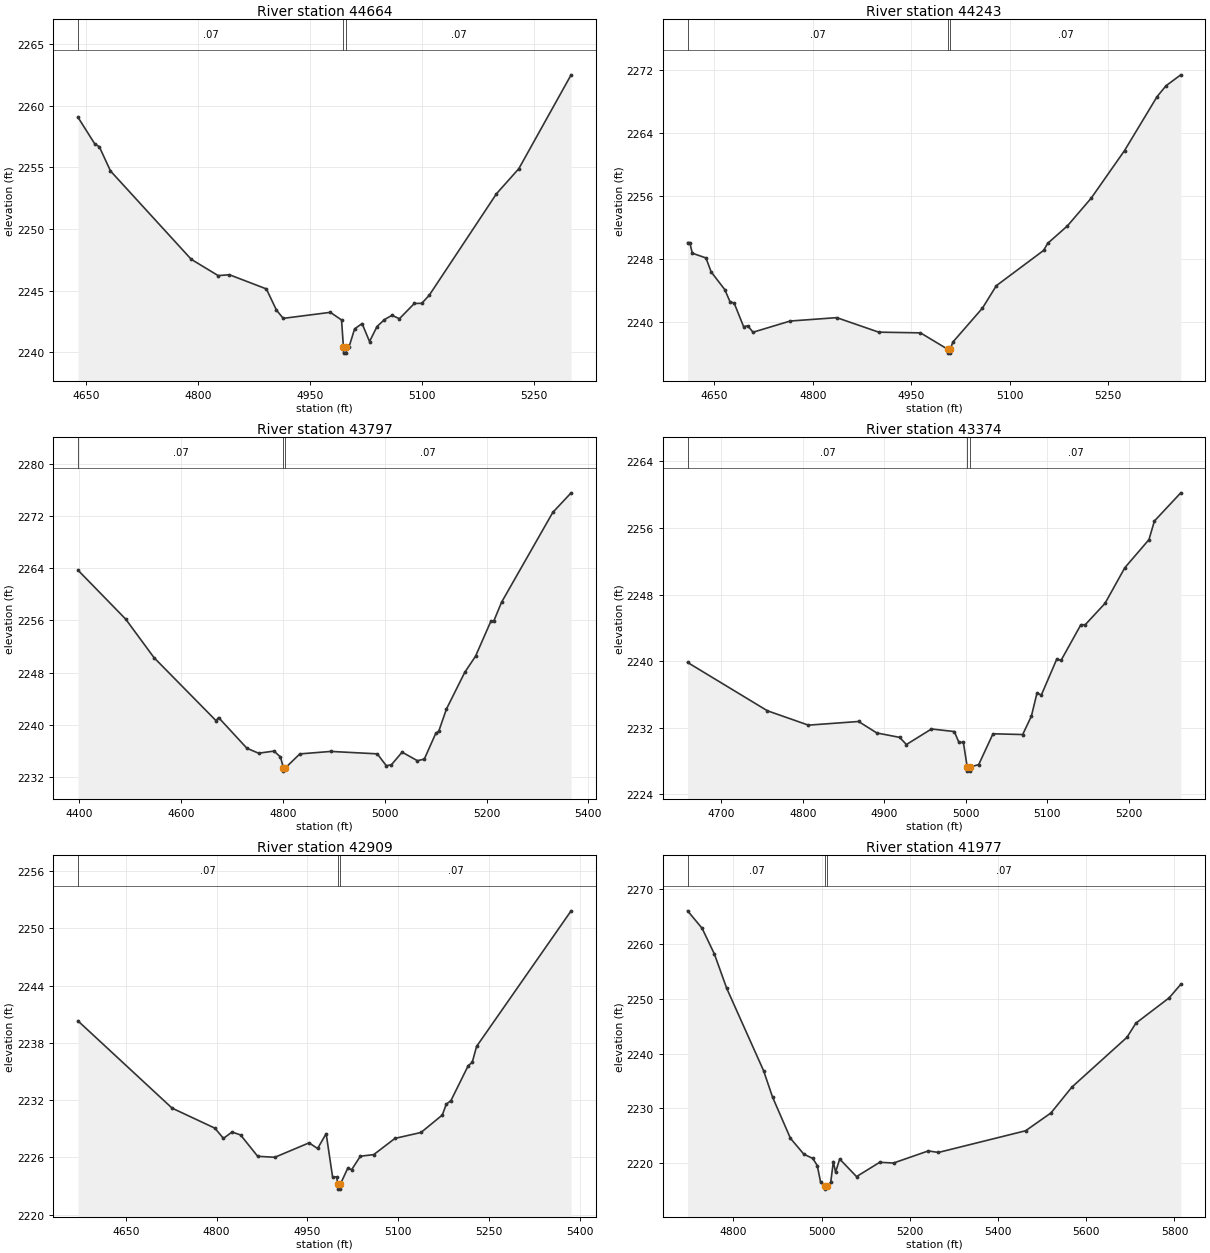
Type RM Length L Ch R = 1,44664,421,421,421
BEGIN DESCRIPTION:
North Fork Guadalupe River 82.0
END DESCRIPTION:
XS GIS Cut Line= 3
      1763775.02     13945325.03      1763575.00     13945025.00
      1763575.00     13944724.99
#Sta/Elev= 30
  4639.1 2259.07  4661.7 2256.90  4667.7 2256.68  4682.7 2254.71  4790.9 2247.54
  4826.9 2246.22  4842.0 2246.29  4891.5 2245.14  4905.0 2243.42  4914.1 2242.75
  4977.2 2243.24  4992.2 2242.62  4994.7 2240.43  4994.9 2239.93  4998.4 2239.93
  4998.7 2240.43  5002.2 2240.43  5009.7 2241.90  5019.7 2242.33  5029.7 2240.87
  5039.7 2242.09  5049.7 2242.65  5059.7 2243.00  5069.7 2242.72  5089.7 2243.96
  5099.7 2243.97  5109.7 2244.63  5199.7 2252.86  5229.7 2254.90  5299.7 2262.51
#Mann=3,-1,0
  4639.1    0.07       0  4994.7    0.05       0  4998.7    0.07       0
Bank Sta=4994.7,4998.7
Exp/Cntr=0.3,0.1

Type RM Length L Ch R = 1,44243,446,446,446
BEGIN DESCRIPTION:
North Fork Guadalupe River 81.0
END DESCRIPTION:
XS GIS Cut Line= 3
      1764175.02     13945125.02      1763925.00     13944825.00
      1763725.00     13944524.99
#Sta/Elev= 30
  4609.4 2250.09  4612.7 2250.09  4616.6 2248.74  4637.4 2248.14  4645.2 2246.38
  4666.0 2244.13  4673.9 2242.61  4680.4 2242.40  4694.7 2239.43  4701.2 2239.53
  4709.0 2238.72  4765.6 2240.14  4836.6 2240.57  4900.4 2238.73  4964.1 2238.64
  5005.4 2236.57  5005.7 2236.07  5009.2 2236.07  5009.4 2236.57  5013.5 2237.48
  5058.5 2241.78  5079.6 2244.62  5151.7 2249.10  5157.7 2249.98  5187.7 2252.19
  5223.8 2255.69  5274.9 2261.76  5324.4 2268.59  5338.0 2269.97  5360.5 2271.36
#Mann=3,-1,0
  4609.4    0.07       0  5005.4    0.05       0  5009.4    0.07       0
Bank Sta=5005.4,5009.4
Exp/Cntr=0.3,0.1

Type RM Length L Ch R = 1,43797,423,423,423
BEGIN DESCRIPTION:
North Fork Guadalupe River 80.0
END DESCRIPTION:
XS GIS Cut Line= 3
      1764225.00     13945274.98      1764325.00     13944675.00
      1764125.01     13944375.01
#Sta/Elev= 30
  4397.3 2263.72  4491.1 2256.21  4546.8 2250.30  4668.5 2240.65  4673.5 2241.13
  4729.3 2236.41  4752.1 2235.66  4782.5 2235.98  4795.2 2235.07  4800.8 2233.41
  4801.0 2232.91  4804.8 2233.41  4833.2 2235.55  4894.0 2235.93  4985.3 2235.56
  5003.0 2233.74  5013.1 2233.89  5034.1 2235.82  5064.1 2234.51  5077.7 2234.75
  5100.2 2238.70  5106.2 2239.05  5121.2 2242.43  5157.3 2248.07  5178.3 2250.52
  5208.4 2255.87  5214.4 2255.95  5229.4 2258.79  5330.1 2272.57  5366.1 2275.57
#Mann=3,-1,0
  4397.3    0.07       0  4800.8    0.05       0  4804.8    0.07       0
Bank Sta=4800.8,4804.8
Exp/Cntr=0.3,0.1

Type RM Length L Ch R = 1,43374,465,465,465
BEGIN DESCRIPTION:
North Fork Guadalupe River 79.0
END DESCRIPTION:
XS GIS Cut Line= 3
      1764525.02     13944974.97      1764675.00     13944675.00
      1764575.01     13944425.03
#Sta/Elev= 30
  4658.9 2239.83  4756.7 2234.02  4807.0 2232.29  4868.5 2232.73  4890.9 2231.35
  4918.8 2230.82  4927.2 2229.96  4957.9 2231.83  4985.9 2231.52  4991.5 2230.22
  4997.0 2230.22  5001.7 2227.26  5001.9 2226.76  5005.4 2226.76  5005.7 2227.26
  5015.8 2227.55  5033.3 2231.25  5069.7 2231.16  5080.4 2233.38  5087.2 2236.13
  5092.6 2235.92  5111.4 2240.21  5116.8 2240.09  5141.0 2244.36  5146.4 2244.37
  5170.6 2246.93  5194.9 2251.22  5224.5 2254.60  5231.2 2256.84  5263.5 2260.23
#Mann=3,-1,0
  4658.9    0.07       0  5001.7    0.05       0  5005.7    0.07       0
Bank Sta=5001.7,5005.7
Exp/Cntr=0.3,0.1

Type RM Length L Ch R = 1,42909,932,932,932
BEGIN DESCRIPTION:
North Fork Guadalupe River 78.0
END DESCRIPTION:
XS GIS Cut Line= 3
      1765425.00     13944925.00      1765125.00     13944625.00
      1764824.99     13944374.99
#Sta/Elev= 30
  4570.9 2240.31  4726.5 2231.16  4797.2 2229.06  4811.3 2227.99  4825.5 2228.66
  4839.6 2228.35  4867.9 2226.11  4896.2 2226.01  4952.7 2227.52  4966.9 2226.93
  4981.0 2228.49  4991.6 2223.95  4998.4 2223.95  5000.3 2223.17  5000.6 2222.67
  5004.1 2222.67  5004.3 2223.17  5016.6 2224.85  5023.2 2224.72  5037.5 2226.12
  5059.6 2226.29  5094.7 2227.99  5137.7 2228.61  5172.9 2230.44  5179.4 2231.57
  5187.2 2231.96  5215.8 2235.63  5222.3 2235.95  5229.5 2237.63  5385.7 2251.85
#Mann=3,-1,0
  4570.9    0.07       0  5000.3    0.05       0  5004.3    0.07       0
Bank Sta=5000.3,5004.3
Exp/Cntr=0.3,0.1

Type RM Length L Ch R = 1,41977,466,466,466
BEGIN DESCRIPTION:
North Fork Guadalupe River 77.0
END DESCRIPTION:
XS GIS Cut Line= 3
      1765924.97     13944174.99      1765625.00     13944125.00
      1764825.05     13944274.99
#Sta/Elev= 30
  4696.3 2266.08  4729.2 2262.89  4757.1 2258.18  4785.0 2251.92  4868.6 2236.87
  4888.9 2232.05  4929.4 2224.53  4959.9 2221.62  4980.1 2220.85  4990.3 2219.54
  4997.9 2216.48  5008.5 2215.74  5008.8 2215.24  5012.6 2215.74  5020.8 2216.49
  5026.7 2220.27  5031.8 2218.34  5041.1 2220.74  5079.3 2217.53  5131.8 2220.14
  5163.2 2220.01  5242.0 2222.22  5264.9 2221.94  5462.5 2225.90  5520.1 2229.16
  5567.6 2233.89  5692.3 2242.97  5712.6 2245.56  5788.1 2250.19  5814.3 2252.65
#Mann=3,-1,0
  4696.3    0.07       0  5008.5    0.05       0  5012.6    0.07       0
Bank Sta=5008.5,5012.6
Exp/Cntr=0.3,0.1

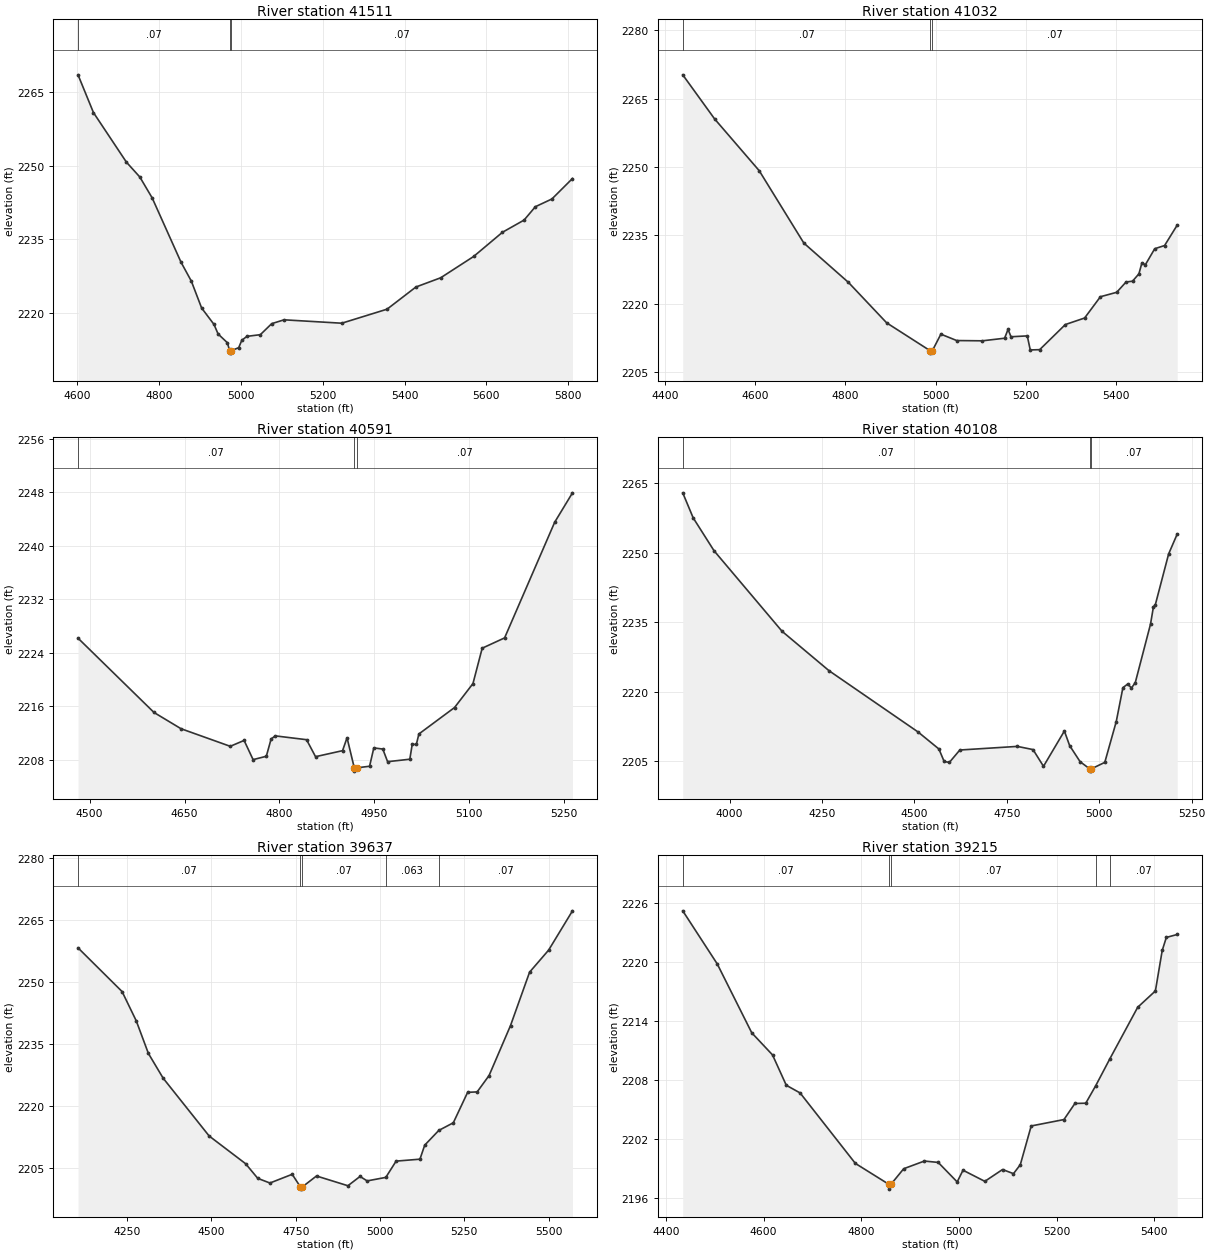
Type RM Length L Ch R = 1,41511,479,479,479
BEGIN DESCRIPTION:
North Fork Guadalupe River 76.0
END DESCRIPTION:
XS GIS Cut Line= 3
      1766075.00     13943725.00      1765675.00     13943675.00
      1764875.04     13943774.99
#Sta/Elev= 30
  4601.3 2268.45  4639.1 2260.77  4719.7 2250.70  4752.5 2247.68  4782.7 2243.43
  4853.2 2230.37  4878.4 2226.53  4903.6 2221.06  4933.9 2217.72  4943.9 2215.78
  4966.6 2214.00  4972.1 2212.39  4972.3 2211.89  4976.3 2212.39  4994.3 2213.00
  5001.9 2214.51  5014.5 2215.30  5047.2 2215.64  5075.0 2217.88  5105.2 2218.66
  5246.3 2217.97  5357.1 2220.82  5427.7 2225.33  5488.2 2227.20  5568.8 2231.53
  5639.3 2236.45  5692.2 2238.93  5719.9 2241.65  5760.3 2243.22  5810.6 2247.38
#Mann=3,-1,0
  4601.3    0.07       0  4972.1    0.05       0  4976.3    0.07       0
Bank Sta=4972.1,4976.3
Exp/Cntr=0.3,0.1

Type RM Length L Ch R = 1,41032,441,441,441
BEGIN DESCRIPTION:
North Fork Guadalupe River 75.0
END DESCRIPTION:
XS GIS Cut Line= 3
      1766174.98     13943624.98      1765775.00     13943225.00
      1765374.97     13942874.97
#Sta/Elev= 30
  4439.0 2270.22  4509.7 2260.55  4608.7 2249.19  4707.7 2233.32  4806.7 2224.69
  4891.5 2215.82  4988.4 2209.68  4988.7 2209.18  4992.7 2209.68  5011.8 2213.34
  5046.9 2211.94  5103.8 2211.88  5153.2 2212.45  5160.8 2214.39  5167.4 2212.77
  5203.5 2212.96  5210.1 2209.88  5231.0 2209.94  5288.0 2215.45  5330.7 2216.88
  5365.8 2221.55  5401.9 2222.52  5422.7 2224.78  5437.0 2224.96  5451.2 2226.57
  5457.9 2228.98  5465.5 2228.56  5486.3 2232.08  5508.2 2232.78  5536.2 2237.26
#Mann=3,-1,0
  4439.0    0.07       0  4988.4    0.05       0  4992.7    0.07       0
Bank Sta=4988.4,4992.7
Exp/Cntr=0.3,0.1

Type RM Length L Ch R = 1,40591,483,483,483
BEGIN DESCRIPTION:
North Fork Guadalupe River 74.0
END DESCRIPTION:
XS GIS Cut Line= 3
      1766125.02     13943175.02      1765725.00     13942825.00
      1765525.03     13942675.02
#Sta/Elev= 30
  4481.6 2226.16  4601.7 2215.05  4644.4 2212.62  4722.2 2209.99  4744.1 2210.87
  4758.3 2208.00  4779.2 2208.50  4786.8 2211.09  4793.4 2211.55  4842.8 2210.98
  4857.0 2208.44  4899.7 2209.34  4906.8 2211.27  4918.2 2206.78  4918.5 2206.28
  4922.9 2206.78  4942.4 2207.01  4949.1 2209.75  4963.3 2209.58  4970.9 2207.69
  5006.0 2208.06  5009.8 2210.28  5016.3 2210.28  5020.4 2211.84  5076.7 2215.79
  5105.8 2219.37  5120.4 2224.66  5155.8 2226.20  5235.0 2243.50  5263.1 2247.89
#Mann=3,-1,0
  4481.6    0.07       0  4918.2    0.05       0  4922.9    0.07       0
Bank Sta=4918.2,4922.9
Exp/Cntr=0.3,0.1

Type RM Length L Ch R = 1,40108,471,471,471
BEGIN DESCRIPTION:
North Fork Guadalupe River 73.0
END DESCRIPTION:
XS GIS Cut Line= 3
      1766724.97     13943224.97      1765925.00     13942425.00
      1765724.99     13942375.00
#Sta/Elev= 30
  3873.3 2262.96  3901.5 2257.56  3958.1 2250.44  4142.0 2233.06  4269.2 2224.54
  4509.7 2211.33  4566.2 2207.65  4580.4 2204.95  4594.5 2204.75  4622.8 2207.43
  4778.4 2208.21  4820.8 2207.52  4849.1 2203.91  4905.6 2211.53  4919.8 2208.38
  4948.1 2204.91  4973.9 2203.37  4974.3 2202.87  4978.7 2203.37  5014.9 2204.76
  5045.9 2213.57  5063.9 2220.89  5076.8 2221.67  5087.1 2220.82  5097.4 2221.99
  5138.6 2234.62  5146.4 2238.31  5151.5 2238.77  5187.6 2249.77  5210.8 2254.06
#Mann=3,-1,0
  3873.3    0.07       0  4973.9    0.05       0  4978.7    0.07       0
Bank Sta=4973.9,4978.7
Exp/Cntr=0.3,0.1

Type RM Length L Ch R = 1,39637,422,422,422
BEGIN DESCRIPTION:
North Fork Guadalupe River 72.0
END DESCRIPTION:
XS GIS Cut Line= 3
      1767025.02     13942625.01      1766275.00     13942125.00
      1765875.00     13941725.00
#Sta/Elev= 30
  4104.0 2258.29  4234.7 2247.71  4276.8 2240.62  4312.8 2232.73  4356.4 2226.76
  4493.1 2212.74  4601.3 2206.03  4637.3 2202.49  4673.4 2201.36  4739.5 2203.47
  4764.1 2200.38  4764.5 2199.88  4768.9 2200.38  4811.6 2203.06  4904.8 2200.70
  4940.8 2202.95  4961.8 2201.87  5017.2 2202.72  5047.8 2206.66  5118.5 2207.13
  5132.7 2210.53  5174.4 2214.09  5217.5 2215.94  5260.0 2223.31  5288.3 2223.42
  5323.6 2227.38  5387.2 2239.47  5443.8 2252.40  5500.4 2257.75  5571.1 2267.25
#Mann=5,-1,0
  4104.0    0.07       0  4764.1    0.05       0  4768.9    0.07       0
  5017.2   0.063       0  5174.4    0.07       0
Bank Sta=4764.1,4768.9
Exp/Cntr=0.3,0.1

Type RM Length L Ch R = 1,39215,421,421,421
BEGIN DESCRIPTION:
North Fork Guadalupe River 71.0
END DESCRIPTION:
XS GIS Cut Line= 3
      1767025.01     13942325.01      1766625.00     13941925.00
      1766225.01     13941725.01
#Sta/Elev= 30
  4434.3 2225.19  4505.0 2219.80  4575.7 2212.81  4618.2 2210.57  4646.4 2207.49
  4674.7 2206.71  4787.9 2199.56  4856.1 2197.45  4856.5 2196.95  4861.0 2197.45
  4886.9 2199.02  4929.3 2199.80  4957.6 2199.66  4996.5 2197.68  5008.4 2198.87
  5053.1 2197.74  5089.4 2198.94  5111.8 2198.52  5125.8 2199.43  5148.1 2203.36
  5215.2 2204.01  5237.6 2205.64  5259.9 2205.67  5280.2 2207.44  5309.5 2210.20
  5366.2 2215.40  5402.5 2217.06  5416.5 2221.17  5424.9 2222.49  5447.2 2222.79
#Mann=5,-1,0
  4434.3    0.07       0  4856.1    0.05       0  4861.0    0.07       0
  5280.2   0.063       0  5309.5    0.07       0
Bank Sta=4856.1,4861
Exp/Cntr=0.3,0.1

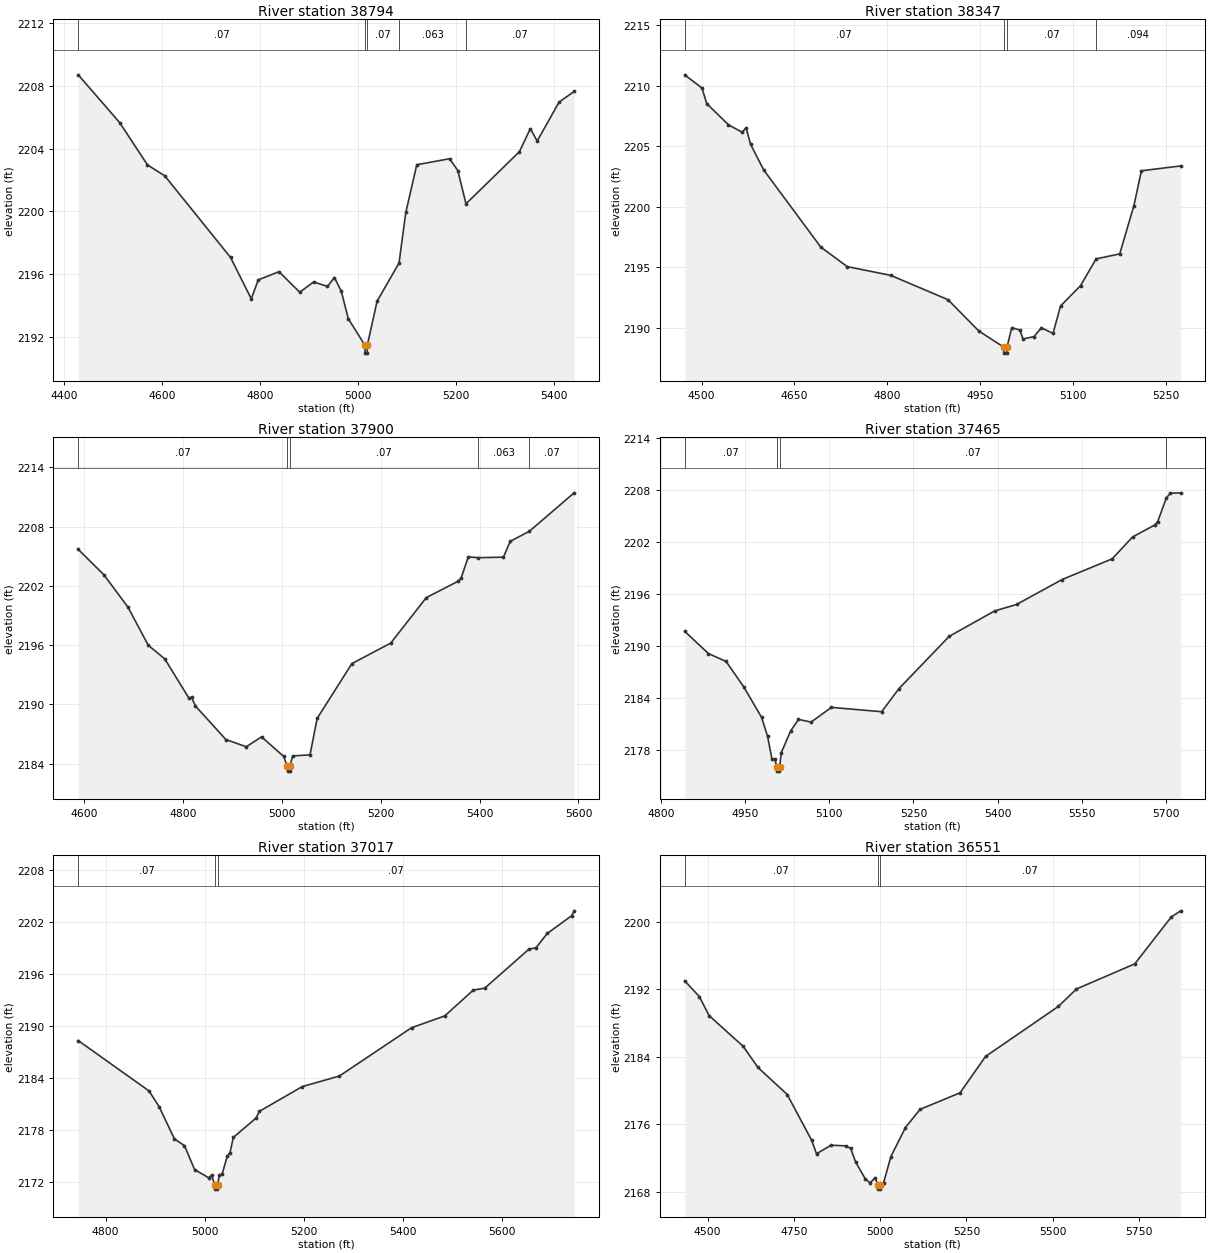
Type RM Length L Ch R = 1,38794,447,447,447
BEGIN DESCRIPTION:
North Fork Guadalupe River 70.0
END DESCRIPTION:
XS GIS Cut Line= 3
      1767274.99     13942024.99      1766875.00     13941625.00
      1766474.99     13941425.00
#Sta/Elev= 30
  4428.2 2208.70  4513.0 2205.65  4569.6 2202.96  4605.0 2202.26  4739.3 2197.06
  4781.7 2194.42  4795.9 2195.63  4838.3 2196.15  4880.7 2194.84  4909.0 2195.50
  4937.3 2195.21  4951.5 2195.78  4965.6 2194.90  4979.7 2193.16  5013.8 2191.46
  5014.1 2190.96  5018.3 2190.96  5018.7 2191.46  5038.6 2194.27  5083.4 2196.70
  5097.3 2199.93  5119.7 2202.97  5186.7 2203.35  5203.5 2202.60  5220.2 2200.48
  5329.3 2203.80  5351.6 2205.27  5365.6 2204.48  5410.3 2206.96  5441.1 2207.64
#Mann=5,-1,0
  4428.2    0.07       0  5013.8    0.05       0  5018.7    0.07       0
  5083.4   0.063       0  5220.2    0.07       0
Bank Sta=5013.8,5018.7
Exp/Cntr=0.3,0.1

Type RM Length L Ch R = 1,38347,447,447,447
BEGIN DESCRIPTION:
North Fork Guadalupe River 69.0
END DESCRIPTION:
XS GIS Cut Line= 3
      1767575.02     13941775.03      1767225.00     13941375.00
      1767125.00     13941125.00
#Sta/Elev= 30
  4472.7 2210.89  4500.7 2209.80  4508.3 2208.51  4543.4 2206.77  4565.3 2206.15
  4571.9 2206.52  4579.0 2205.17  4600.4 2203.03  4692.5 2196.67  4735.2 2195.06
  4805.4 2194.34  4897.9 2192.33  4947.8 2189.74  4987.8 2188.42  4988.2 2187.92
  4992.7 2187.92  4993.1 2188.42  5000.9 2190.02  5013.7 2189.83  5019.1 2189.09
  5036.6 2189.28  5048.7 2190.01  5067.5 2189.55  5079.6 2191.81  5111.9 2193.49
  5137.1 2195.70  5175.2 2196.11  5198.1 2200.10  5210.2 2202.97  5273.5 2203.37
#Mann=4,-1,0
  4472.7    0.07       0  4987.8    0.05       0  4993.1    0.07       0
  5137.1   0.094       0
Bank Sta=4987.8,4993.1
Exp/Cntr=0.3,0.1

Type RM Length L Ch R = 1,37900,435,435,435
BEGIN DESCRIPTION:
North Fork Guadalupe River 68.0
END DESCRIPTION:
XS GIS Cut Line= 4
      1767724.99     13941624.96      1767625.00     13941225.00
      1767425.00     13940975.00      1767255.60     13940763.25
#Sta/Elev= 30
  4587.7 2205.70  4639.2 2203.15  4688.2 2199.86  4729.4 2195.99  4762.9 2194.60
  4811.9 2190.61  4817.0 2190.74  4824.7 2189.84  4886.6 2186.43  4927.8 2185.70
  4958.7 2186.70  5003.2 2184.73  5010.9 2183.73  5011.3 2183.23  5015.8 2183.23
  5016.2 2183.73  5021.6 2184.77  5056.8 2184.88  5071.2 2188.57  5141.6 2194.13
  5220.1 2196.20  5292.1 2200.81  5356.1 2202.46  5362.5 2202.78  5377.0 2204.94
  5397.1 2204.86  5448.2 2204.91  5461.8 2206.51  5500.8 2207.54  5591.3 2211.43
#Mann=5,-1,0
  4587.7    0.07       0  5010.9    0.05       0  5016.2    0.07       0
  5397.1   0.063       0  5500.8    0.07       0
Bank Sta=5010.9,5016.2
Exp/Cntr=0.3,0.1

Type RM Length L Ch R = 1,37465,448,448,448
BEGIN DESCRIPTION:
North Fork Guadalupe River 67.0
END DESCRIPTION:
XS GIS Cut Line= 4
      1768075.00     13941374.99      1768025.00     13941225.00
      1767875.00     13940925.00      1767700.50     13940576.01
#Sta/Elev= 30
  4842.3 2191.67  4884.5 2189.10  4916.1 2188.18  4947.7 2185.23  4979.3 2181.72
  4989.9 2179.55  4997.8 2176.92  5003.2 2176.92  5006.1 2176.00  5006.5 2175.50
  5011.0 2175.50  5011.5 2176.00  5014.4 2177.63  5031.2 2180.16  5045.1 2181.48
  5067.5 2181.17  5103.8 2182.87  5193.3 2182.37  5224.0 2185.03  5313.5 2191.08
  5394.5 2194.02  5433.6 2194.77  5514.7 2197.65  5604.1 2200.05  5640.5 2202.58
  5679.6 2203.95  5685.2 2204.36  5700.5 2207.07  5707.6 2207.63  5726.0 2207.68
#Mann=4,-1,0
  4842.3    0.07       0  5006.1    0.05       0  5011.5    0.07       0
  5700.5   0.063       0
Bank Sta=5006.1,5011.5
Exp/Cntr=0.3,0.1

Type RM Length L Ch R = 1,37017,466,466,466
BEGIN DESCRIPTION:
North Fork Guadalupe River 66.0
END DESCRIPTION:
XS GIS Cut Line= 4
      1768374.99     13941325.03      1768425.00     13941075.00
      1768225.00     13940725.00      1768055.57     13940428.49
#Sta/Elev= 30
  4745.0 2188.30  4887.8 2182.49  4908.2 2180.67  4938.8 2176.97  4959.2 2176.18
  4979.6 2173.43  5007.9 2172.48  5013.7 2172.78  5020.3 2171.67  5020.7 2171.17
  5025.3 2171.17  5025.8 2171.67  5029.5 2172.75  5035.3 2172.95  5045.3 2174.95
  5051.1 2175.39  5057.6 2177.13  5103.6 2179.37  5110.1 2180.14  5196.5 2182.99
  5271.4 2184.21  5416.8 2189.78  5483.7 2191.14  5541.3 2194.12  5564.3 2194.34
  5652.9 2198.81  5668.0 2199.02  5690.3 2200.65  5739.3 2202.68  5744.6 2203.26
#Mann=3,-1,0
  4745.0    0.07       0  5020.3    0.05       0  5025.8    0.07       0
Bank Sta=5020.3,5025.8
Exp/Cntr=0.3,0.1

Type RM Length L Ch R = 1,36551,437,437,437
BEGIN DESCRIPTION:
North Fork Guadalupe River 65.0
END DESCRIPTION:
XS GIS Cut Line= 4
      1768474.98     13941425.02      1768875.00     13941025.00
      1768775.00     13940725.00      1768599.63     13940198.90
#Sta/Elev= 30
  4433.9 2193.01  4476.4 2191.14  4504.6 2188.89  4603.6 2185.24  4646.1 2182.75
  4730.9 2179.55  4801.6 2174.13  4815.8 2172.54  4858.2 2173.55  4900.6 2173.47
  4914.8 2173.16  4928.9 2171.58  4957.2 2169.55  4971.3 2169.09  4985.5 2169.72
  4993.3 2168.85  4993.7 2168.35  4998.4 2168.35  4998.9 2168.85  5010.2 2169.12
  5031.2 2172.21  5073.4 2175.64  5115.6 2177.79  5231.5 2179.75  5305.3 2184.05
  5516.1 2189.97  5568.8 2192.04  5737.5 2195.01  5842.9 2200.54  5870.4 2201.29
#Mann=3,-1,0
  4433.9    0.07       0  4993.3    0.05       0  4998.9    0.07       0
Bank Sta=4993.3,4998.9
Exp/Cntr=0.3,0.1

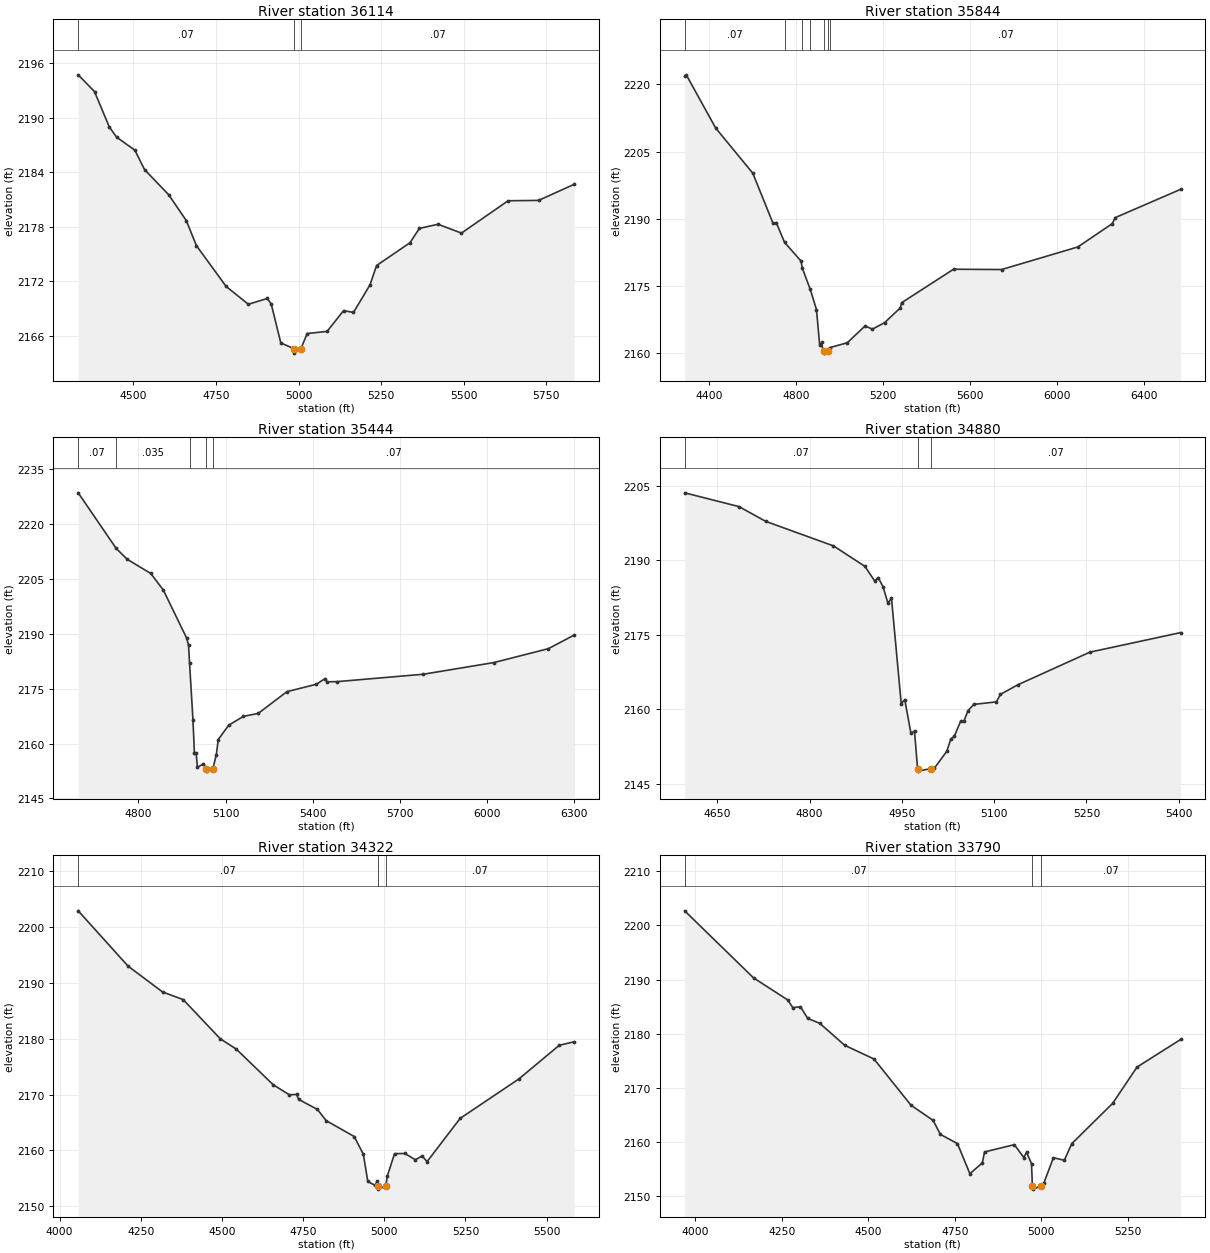
Type RM Length L Ch R = 1,36114,270,270,270
BEGIN DESCRIPTION:
Mapping XS 287935f2
END DESCRIPTION:
XS GIS Cut Line= 4
      1768541.27     13941509.67      1769062.12     13941252.72
      1769423.23     13941242.30      1769832.96     13940860.35
#Sta/Elev= 30
  4332.6 2194.74  4382.0 2192.89  4426.9 2188.99  4449.4 2187.86  4504.0 2186.45
  4533.6 2184.30  4606.5 2181.54  4660.1 2178.68  4690.8 2175.92  4780.6 2171.44
  4847.9 2169.47  4905.4 2170.11  4917.3 2169.49  4946.3 2165.21  4985.6 2164.59
  4986.1 2164.09  5007.1 2164.59  5026.3 2166.25  5086.3 2166.48  5136.4 2168.77
  5166.4 2168.57  5216.4 2171.61  5236.4 2173.74  5337.6 2176.25  5366.0 2177.83
  5422.6 2178.28  5493.5 2177.31  5634.7 2180.87  5727.0 2180.91  5834.8 2182.68
#Mann=3,-1,0
  4332.6    0.07       0  4985.6    0.05       0  5007.1    0.07       0
Bank Sta=4985.6,5007.1
Exp/Cntr=0.3,0.1

Type RM Length L Ch R = 1,35844,400,400,400
BEGIN DESCRIPTION:
North Fork Guadalupe River 64.0
END DESCRIPTION:
XS GIS Cut Line= 5
      1768524.96     13941925.03      1769028.93     13941544.27
      1769151.00     13941439.83      1769666.40     13941179.45
      1770193.15     13940433.88
#Sta/Elev= 30
  4286.4 2221.81  4293.7 2222.15  4429.0 2210.26  4599.8 2200.17  4693.3 2188.94
  4707.9 2189.13  4746.0 2184.71  4822.3 2180.51  4827.4 2179.00  4864.5 2174.18
  4893.1 2169.67  4907.7 2161.77  4918.0 2162.38  4922.0 2160.52  4925.5 2160.45
  4926.0 2159.95  4947.0 2160.45  4955.8 2161.20  5035.1 2162.27  5116.8 2166.03
  5150.4 2165.31  5206.1 2166.75  5278.6 2170.04  5284.8 2171.21  5523.8 2178.70
  5745.1 2178.63  6095.9 2183.68  6253.5 2188.86  6268.3 2190.24  6569.0 2196.56
#Mann=7,-1,0
  4286.4    0.07       0  4746.0   0.035       0  4827.4    0.07       0
  4864.5   0.035       0  4925.5    0.05       0  4947.0   0.035       0
  4955.8    0.07       0
Bank Sta=4925.5,4947
Exp/Cntr=0.3,0.1

Type RM Length L Ch R = 1,35444,564,564,564
BEGIN DESCRIPTION:
North Fork Guadalupe River 63.0
END DESCRIPTION:
XS GIS Cut Line= 3
      1769125.01     13942124.98      1769325.00     13941775.00
      1770060.01     13940696.66
#Sta/Elev= 30
  4592.7 2228.42  4723.6 2213.23  4761.8 2210.26  4842.5 2206.42  4885.7 2201.91
  4966.3 2188.76  4972.8 2186.78  4976.2 2181.98  4987.9 2166.49  4992.9 2157.42
  4998.8 2157.42  5003.3 2153.50  5024.2 2154.48  5034.5 2152.97  5035.0 2152.47
  5056.0 2152.97  5068.4 2156.95  5075.1 2161.10  5111.0 2165.00  5161.8 2167.42
  5212.7 2168.22  5311.5 2174.16  5413.2 2176.18  5443.0 2177.74  5449.1 2176.84
  5485.0 2176.90  5781.1 2178.91  6024.5 2182.10  6212.0 2185.89  6300.8 2189.60
#Mann=5,-1,0
  4592.7    0.07       0  4723.6   0.035       0  4976.2    0.07       0
  5034.5    0.05       0  5056.0    0.07       0
Bank Sta=5034.5,5056
Exp/Cntr=0.3,0.1

Type RM Length L Ch R = 1,34880,558,558,558
BEGIN DESCRIPTION:
North Fork Guadalupe River 62.0
END DESCRIPTION:
XS GIS Cut Line= 3
      1769675.00     13942174.99      1769875.00     13941825.00
      1769675.01     13941475.02
#Sta/Elev= 30
  4597.0 2203.54  4685.5 2200.76  4728.7 2197.80  4838.9 2192.86  4890.0 2188.74
  4905.8 2185.81  4911.6 2186.49  4919.5 2184.62  4927.4 2181.35  4933.2 2182.33
  4949.0 2161.10  4954.8 2161.92  4964.8 2155.13  4970.6 2155.62  4975.6 2148.03
  4976.1 2147.53  4997.2 2148.03  5003.0 2148.14  5023.1 2151.53  5029.6 2153.95
  5035.4 2154.56  5045.5 2157.56  5051.2 2157.69  5057.7 2159.72  5067.1 2160.96
  5103.8 2161.47  5110.2 2162.97  5138.3 2164.89  5255.6 2171.47  5403.2 2175.41
#Mann=3,-1,0
  4597.0    0.07       0  4975.6    0.05       0  4997.2    0.07       0
Bank Sta=4975.6,4997.2
Exp/Cntr=0.3,0.1

Type RM Length L Ch R = 1,34322,532,532,532
BEGIN DESCRIPTION:
North Fork Guadalupe River 61.0
END DESCRIPTION:
XS GIS Cut Line= 4
      1771083.85     13942293.61      1770848.34     13942053.67
      1770375.00     13941675.00      1770175.01     13941125.02
#Sta/Elev= 30
  4057.3 2202.88  4211.0 2192.98  4317.2 2188.36  4380.8 2186.99  4494.6 2180.00
  4544.3 2178.13  4657.9 2171.76  4707.5 2169.96  4730.0 2170.02  4736.4 2169.13
  4794.0 2167.35  4821.2 2165.33  4907.6 2162.49  4935.7 2159.29  4949.3 2154.45
  4971.7 2153.75  4978.1 2154.48  4980.7 2153.58  4981.2 2153.08  5004.3 2153.58
  5009.7 2155.46  5031.6 2159.42  5063.5 2159.46  5095.5 2158.34  5116.7 2159.00
  5132.0 2158.01  5233.8 2165.74  5414.7 2172.80  5539.0 2178.82  5584.9 2179.45
#Mann=3,-1,0
  4057.3    0.07       0  4980.7    0.05       0  5004.3    0.07       0
Bank Sta=4980.7,5004.3
Exp/Cntr=0.3,0.1

Type RM Length L Ch R = 1,33790,558,558,558
BEGIN DESCRIPTION:
North Fork Guadalupe River 60.0
END DESCRIPTION:
XS GIS Cut Line= 3
      1771275.01     13942125.02      1770625.00     13941325.00
      1770425.01     13940975.01
#Sta/Elev= 30
  3969.2 2202.71  4168.2 2190.31  4267.3 2186.22  4281.7 2184.81  4304.0 2184.96
  4324.8 2182.82  4360.0 2181.89  4431.8 2177.84  4516.6 2175.30  4623.6 2166.75
  4687.5 2163.95  4708.4 2161.36  4757.9 2159.65  4793.8 2154.09  4829.8 2156.08
  4836.2 2158.11  4922.4 2159.46  4949.7 2157.08  4957.6 2158.05  4972.0 2155.95
  4974.6 2151.73  4975.1 2151.23  4998.2 2151.73  5007.9 2152.39  5035.3 2157.04
  5066.9 2156.57  5088.5 2159.65  5206.6 2167.10  5277.1 2173.81  5403.1 2178.91
#Mann=3,-1,0
  3969.2    0.07       0  4974.6    0.05       0  4998.2    0.07       0
Bank Sta=4974.6,4998.2
Exp/Cntr=0.3,0.1