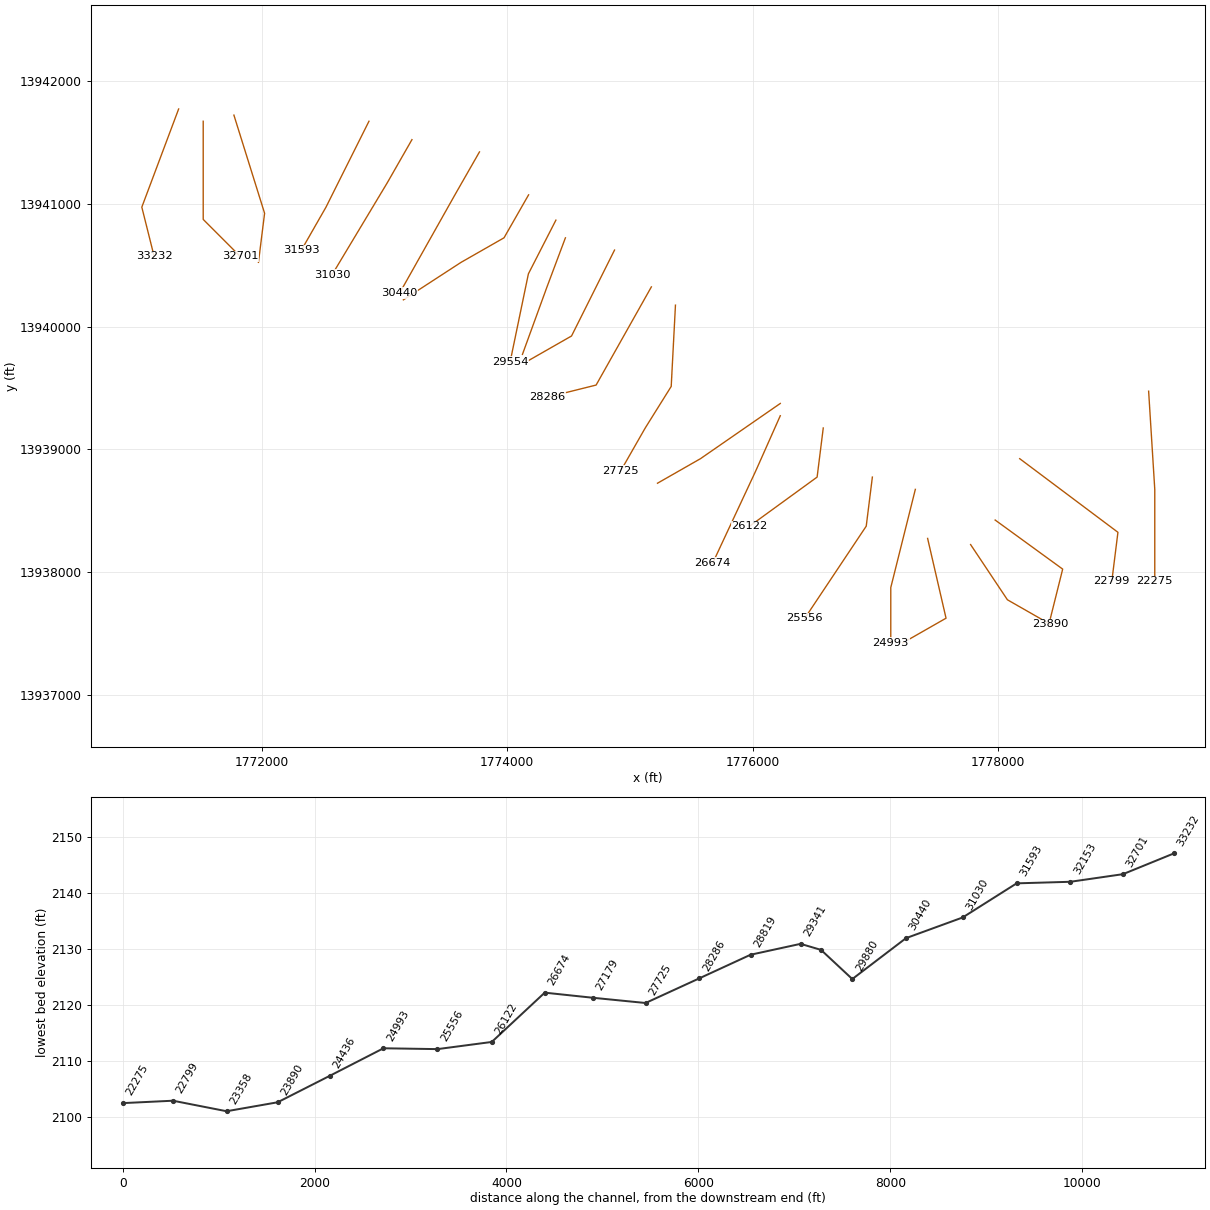
HEC-RAS study North Fork Guadalupe River.prj: North Fork Guadalupe River Base Level Engineering

--- North Fork Guadalupe River.g01 (geometry) --- (continued)

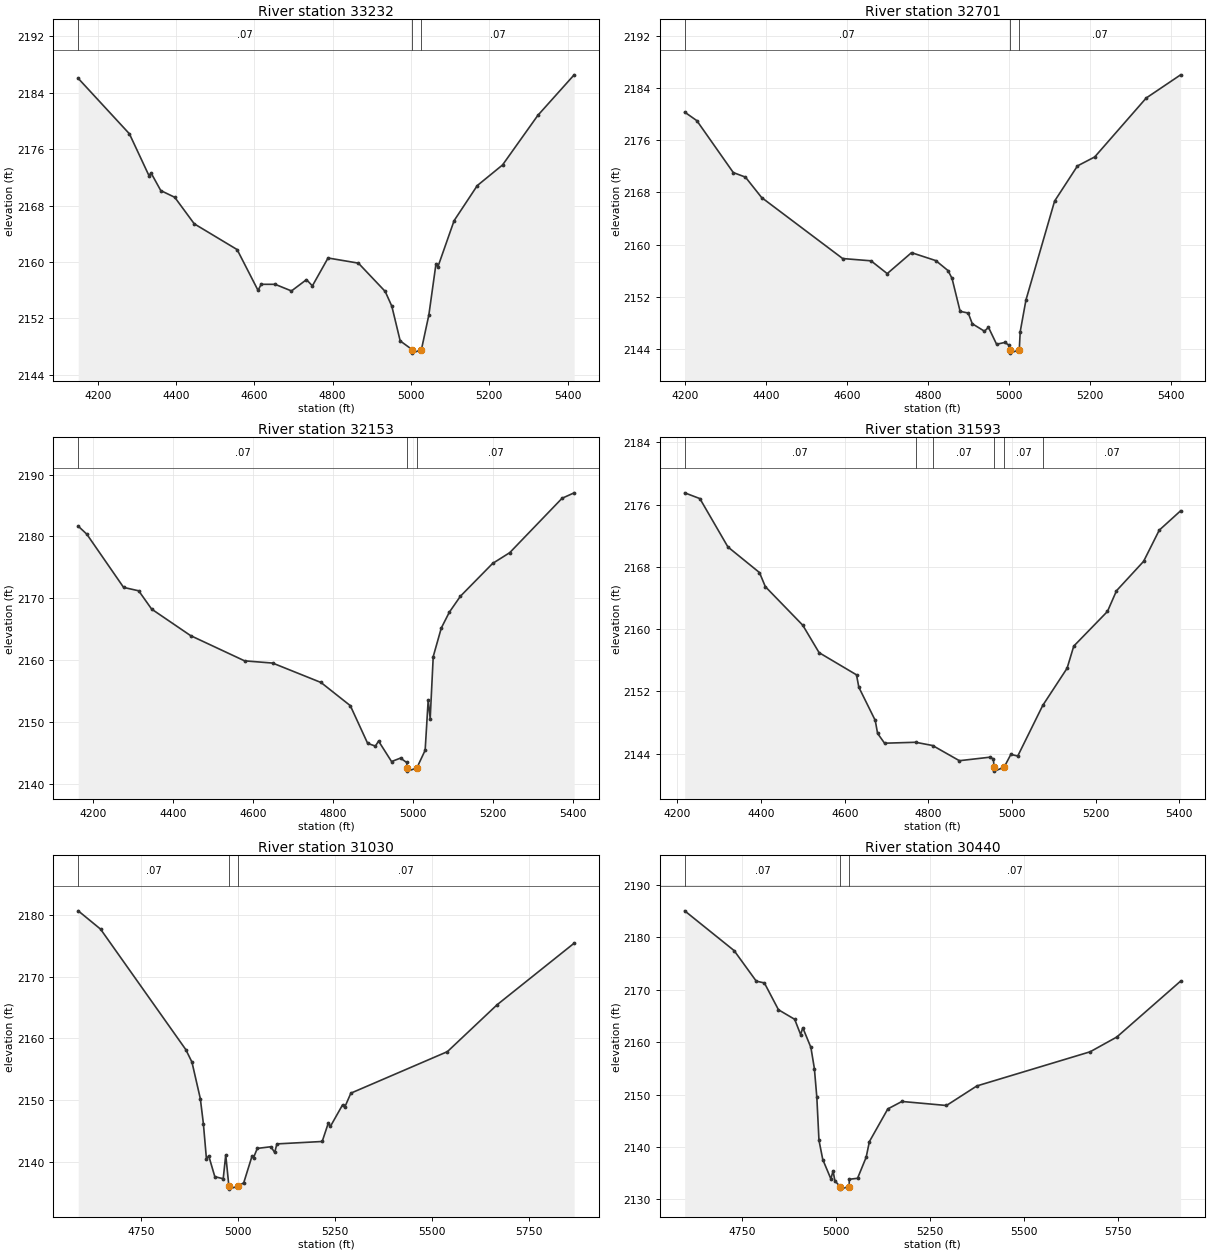
Type RM Length L Ch R = 1,33232,531,531,531
BEGIN DESCRIPTION:
North Fork Guadalupe River 59.0
END DESCRIPTION:
XS GIS Cut Line= 3
      1771325.00     13941775.01      1771025.00     13940975.00
      1771124.99     13940575.02
#Sta/Elev= 30
  4150.1 2186.02  4280.9 2178.16  4330.8 2172.24  4336.1 2172.62  4361.0 2170.12
  4396.6 2169.17  4446.5 2165.41  4556.0 2161.76  4609.4 2155.98  4617.4 2156.84
  4653.0 2156.84  4694.8 2155.90  4733.1 2157.50  4748.2 2156.62  4788.2 2160.57
  4865.7 2159.84  4934.2 2155.83  4951.1 2153.74  4972.5 2148.82  5003.0 2147.59
  5003.5 2147.09  5026.7 2147.59  5045.7 2152.50  5063.8 2159.70  5068.9 2159.33
  5110.2 2165.86  5169.4 2170.83  5233.9 2173.75  5324.1 2180.78  5416.8 2186.52
#Mann=3,-1,0
  4150.1    0.07       0  5003.0    0.05       0  5026.7    0.07       0
Bank Sta=5003,5026.7
Exp/Cntr=0.3,0.1

Type RM Length L Ch R = 1,32701,548,548,548
BEGIN DESCRIPTION:
North Fork Guadalupe River 58.0
END DESCRIPTION:
XS GIS Cut Line= 3
      1771525.00     13941675.03      1771525.00     13940875.00
      1771825.00     13940575.00
#Sta/Elev= 30
  4199.3 2180.30  4229.3 2178.99  4319.3 2171.04  4349.3 2170.34  4389.3 2167.21
  4589.3 2157.87  4659.3 2157.52  4699.3 2155.56  4759.3 2158.77  4819.3 2157.55
  4849.3 2156.03  4859.3 2154.83  4879.3 2149.78  4899.3 2149.52  4909.3 2147.88
  4939.3 2146.74  4949.3 2147.33  4969.3 2144.74  4989.3 2145.01  4999.3 2144.63
  5001.6 2143.88  5002.1 2143.38  5025.3 2143.88  5027.6 2146.66  5041.8 2151.52
  5112.5 2166.67  5169.0 2172.06  5211.5 2173.43  5338.7 2182.46  5423.6 2186.01
#Mann=3,-1,0
  4199.3    0.07       0  5001.6    0.05       0  5025.3    0.07       0
Bank Sta=5001.6,5025.3
Exp/Cntr=0.3,0.1

Type RM Length L Ch R = 1,32153,560,560,560
BEGIN DESCRIPTION:
North Fork Guadalupe River 57.0
END DESCRIPTION:
XS GIS Cut Line= 3
      1771775.01     13941724.96      1772025.00     13940925.00
      1771975.00     13940525.03
#Sta/Elev= 30
  4162.3 2181.65  4183.7 2180.36  4275.9 2171.74  4313.7 2171.19  4346.1 2168.23
  4443.6 2163.94  4578.7 2159.86  4648.9 2159.50  4769.9 2156.36  4843.3 2152.61
  4886.7 2146.51  4906.1 2146.07  4914.0 2146.88  4946.5 2143.57  4969.0 2144.13
  4984.2 2143.42  4985.9 2142.52  4986.4 2142.02  5009.7 2142.52  5030.6 2145.40
  5038.2 2153.53  5043.2 2150.53  5050.8 2160.55  5071.0 2165.17  5091.1 2167.73
  5118.8 2170.31  5199.5 2175.62  5242.3 2177.36  5373.3 2186.16  5403.5 2187.04
#Mann=3,-1,0
  4162.3    0.07       0  4985.9    0.05       0  5009.7    0.07       0
Bank Sta=4985.9,5009.7
Exp/Cntr=0.3,0.1

Type RM Length L Ch R = 1,31593,563,563,563
BEGIN DESCRIPTION:
North Fork Guadalupe River 56.0
END DESCRIPTION:
XS GIS Cut Line= 3
      1772874.98     13941674.97      1772525.00     13940975.00
      1772325.00     13940625.00
#Sta/Elev= 30
  4217.3 2177.52  4253.6 2176.78  4320.7 2170.56  4396.1 2167.27  4410.1 2165.46
  4499.6 2160.50  4538.7 2156.97  4628.1 2154.12  4633.7 2152.52  4672.9 2148.26
  4678.5 2146.59  4695.2 2145.33  4769.4 2145.45  4810.2 2145.03  4874.1 2143.08
  4946.8 2143.53  4955.2 2143.31  4957.2 2142.24  4957.7 2141.74  4981.0 2142.24
  4997.1 2143.89  5013.6 2143.68  5073.4 2150.19  5131.6 2154.97  5147.5 2157.81
  5228.1 2162.27  5249.7 2164.93  5314.5 2168.71  5351.9 2172.72  5403.0 2175.21
#Mann=6,-1,0
  4217.3    0.07       0  4769.4   0.035       0  4810.2    0.07       0
  4957.2   0.035       0  4981.0    0.07       0  5073.4    0.07       0
Bank Sta=4957.2,4981
Exp/Cntr=0.3,0.1

Type RM Length L Ch R = 1,31030,590,590,590
BEGIN DESCRIPTION:
North Fork Guadalupe River 55.0
END DESCRIPTION:
XS GIS Cut Line= 3
      1773225.01     13941525.02      1773025.00     13941175.00
      1772574.99     13940424.98
#Sta/Elev= 30
  4588.8 2180.62  4646.4 2177.66  4866.0 2158.19  4881.8 2156.18  4903.4 2150.27
  4911.3 2146.22  4919.2 2140.50  4925.0 2141.03  4940.8 2137.65  4962.4 2137.32
  4968.9 2141.17  4977.0 2136.14  4977.5 2135.64  5001.1 2136.14  5015.3 2136.67
  5036.6 2140.97  5040.5 2140.73  5050.2 2142.22  5085.2 2142.49  5095.0 2141.57
  5100.8 2142.95  5217.4 2143.34  5232.9 2146.26  5238.8 2145.80  5269.9 2149.26
  5275.7 2148.91  5291.3 2151.15  5540.0 2157.86  5668.3 2165.45  5866.6 2175.39
#Mann=3,-1,0
  4588.8    0.07       0  4977.0    0.05       0  5001.1    0.07       0
Bank Sta=4977,5001.1
Exp/Cntr=0.3,0.1

Type RM Length L Ch R = 1,30440,560,560,560
BEGIN DESCRIPTION:
North Fork Guadalupe River 54.0
END DESCRIPTION:
XS GIS Cut Line= 3
      1773774.99     13941424.99      1773575.00     13941075.00
      1773124.99     13940274.98
#Sta/Elev= 30
  4596.9 2185.06  4728.6 2177.47  4787.6 2171.64  4809.2 2171.30  4846.7 2166.18
  4889.9 2164.36  4905.7 2161.45  4911.5 2162.75  4933.1 2158.99  4942.4 2154.95
  4948.9 2149.47  4954.6 2141.28  4964.7 2137.60  4986.3 2133.91  4992.1 2135.42
  4997.1 2133.52  5010.9 2132.45  5011.4 2131.95  5035.0 2132.45  5035.4 2133.83
  5057.4 2134.02  5080.3 2138.03  5088.9 2141.02  5138.0 2147.26  5175.6 2148.68
  5294.2 2147.91  5375.1 2151.64  5676.9 2158.16  5748.0 2160.98  5917.9 2171.65
#Mann=3,-1,0
  4596.9    0.07       0  5010.9    0.05       0  5035.0    0.07       0
Bank Sta=5010.9,5035
Exp/Cntr=0.3,0.1

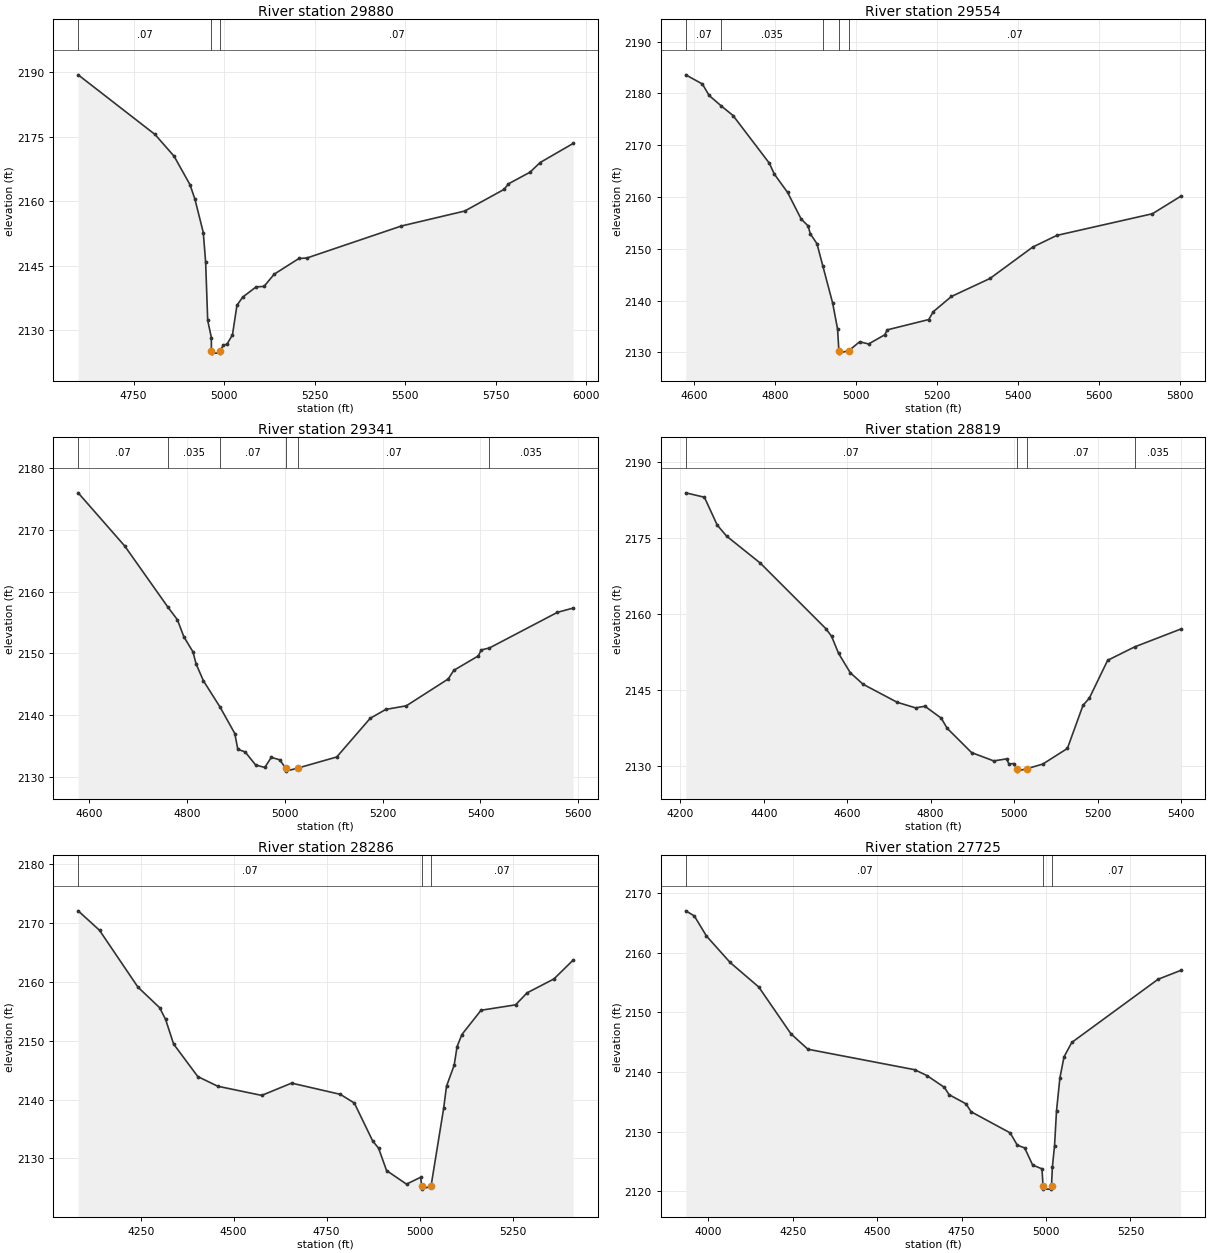
Type RM Length L Ch R = 1,29880,326,326,326
BEGIN DESCRIPTION:
North Fork Guadalupe River 53.0
END DESCRIPTION:
XS GIS Cut Line= 4
      1774174.98     13941074.97      1773975.00     13940725.00
      1773625.00     13940525.00      1773155.23     13940219.43
#Sta/Elev= 30
  4596.9 2189.43  4809.2 2175.54  4861.8 2170.48  4905.7 2163.86  4919.4 2160.45
  4942.4 2152.72  4948.9 2145.82  4954.6 2132.25  4964.7 2128.27  4964.8 2125.14
  4965.3 2124.64  4988.5 2124.64  4989.0 2125.14  4997.1 2126.43  5007.9 2126.73
  5023.0 2128.91  5035.3 2135.75  5051.1 2137.67  5088.5 2140.07  5110.1 2140.17
  5138.2 2143.02  5206.6 2146.68  5228.2 2146.78  5489.1 2154.23  5664.3 2157.72
  5772.9 2162.76  5784.9 2164.04  5844.5 2166.76  5872.5 2169.01  5963.5 2173.45
#Mann=3,-1,0
  4596.9    0.07       0  4964.8    0.05       0  4989.0    0.07       0
Bank Sta=4964.8,4989
Exp/Cntr=0.3,0.1

Type RM Length L Ch R = 1,29554,213,213,213
BEGIN DESCRIPTION:
Mapping XS 57fec1b9
END DESCRIPTION:
XS GIS Cut Line= 3
      1774397.47     13940869.03      1774173.51     13940431.53
      1774025.06     13939715.34
#Sta/Elev= 30
  4579.2 2183.58  4620.3 2181.81  4636.9 2179.60  4666.4 2177.61  4696.1 2175.72
  4785.9 2166.50  4797.9 2164.43  4830.9 2160.87  4864.6 2155.71  4881.2 2154.44
  4887.0 2152.89  4903.4 2150.98  4917.9 2146.68  4942.2 2139.51  4954.4 2134.46
  4957.5 2130.35  4958.0 2129.85  4982.5 2130.35  5008.8 2132.04  5031.0 2131.62
  5070.7 2133.38  5077.4 2134.35  5179.5 2136.33  5190.7 2137.84  5235.7 2140.79
  5330.9 2144.26  5436.4 2150.32  5496.1 2152.58  5732.3 2156.76  5802.1 2160.13
#Mann=5,-1,0
  4579.2    0.07       0  4666.4   0.035       0  4917.9    0.07       0
  4957.5    0.05       0  4982.5    0.07       0
Bank Sta=4957.5,4982.5
Exp/Cntr=0.3,0.1

Type RM Length L Ch R = 1,29341,522,522,522
BEGIN DESCRIPTION:
North Fork Guadalupe River 52.0
END DESCRIPTION:
XS GIS Cut Line= 3
      1774474.99     13940724.97      1774325.00     13940325.00
      1774125.00     13939775.00
#Sta/Elev= 30
  4577.0 2175.98  4672.2 2167.38  4760.5 2157.49  4779.9 2155.45  4793.2 2152.68
  4811.9 2150.23  4818.2 2148.29  4833.3 2145.55  4867.4 2141.28  4897.4 2137.02
  4903.6 2134.47  4918.7 2134.03  4940.1 2131.92  4958.8 2131.53  4972.1 2133.16
  4989.0 2132.77  5001.6 2131.43  5002.1 2130.93  5026.6 2131.43  5105.9 2133.22
  5174.4 2139.48  5206.3 2140.92  5248.2 2141.50  5334.0 2145.85  5345.3 2147.24
  5395.9 2149.60  5401.2 2150.54  5418.4 2150.87  5557.5 2156.64  5589.4 2157.32
#Mann=6,-1,0
  4577.0    0.07       0  4760.5   0.035       0  4867.4    0.07       0
  5001.6    0.05       0  5026.6    0.07       0  5418.4   0.035       0
Bank Sta=5001.6,5026.6
Exp/Cntr=0.3,0.1

Type RM Length L Ch R = 1,28819,533,533,533
BEGIN DESCRIPTION:
North Fork Guadalupe River 51.0
END DESCRIPTION:
XS GIS Cut Line= 3
      1774874.98     13940624.97      1774525.00     13939925.00
      1774175.00     13939725.00
#Sta/Elev= 30
  4213.2 2183.94  4257.9 2183.07  4288.6 2177.57  4311.0 2175.40  4392.0 2170.05
  4548.6 2157.14  4562.5 2155.62  4579.3 2152.24  4607.3 2148.42  4638.0 2146.14
  4719.1 2142.60  4763.8 2141.47  4786.2 2141.80  4825.3 2139.44  4839.3 2137.46
  4898.0 2132.64  4951.1 2131.00  4981.8 2131.40  4987.4 2130.40  4998.7 2130.47
  5006.3 2129.48  5006.8 2128.98  5031.3 2129.48  5068.5 2130.37  5127.5 2133.46
  5164.9 2141.97  5180.1 2143.40  5224.0 2150.87  5288.8 2153.52  5398.9 2157.03
#Mann=4,-1,0
  4213.2    0.07       0  5006.3    0.05       0  5031.3    0.07       0
  5288.8   0.035       0
Bank Sta=5006.3,5031.3
Exp/Cntr=0.3,0.1

Type RM Length L Ch R = 1,28286,561,561,561
BEGIN DESCRIPTION:
North Fork Guadalupe River 50.0
END DESCRIPTION:
XS GIS Cut Line= 3
      1775174.99     13940324.99      1774725.00     13939525.00
      1774324.98     13939424.99
#Sta/Elev= 30
  4082.1 2172.10  4139.5 2168.79  4242.7 2159.13  4301.0 2155.63  4317.0 2153.65
  4338.6 2149.45  4403.7 2143.91  4457.2 2142.27  4575.4 2140.71  4655.8 2142.80
  4786.8 2140.89  4824.4 2139.41  4873.8 2132.95  4889.4 2131.75  4911.0 2127.93
  4964.6 2125.62  5002.5 2126.78  5005.5 2125.27  5006.0 2124.77  5030.5 2125.27
  5064.4 2138.49  5072.1 2142.27  5092.7 2145.84  5100.5 2149.00  5113.4 2151.06
  5164.9 2155.19  5257.7 2156.11  5288.6 2158.15  5360.7 2160.51  5412.3 2163.71
#Mann=3,-1,0
  4082.1    0.07       0  5005.5    0.05       0  5030.5    0.07       0
Bank Sta=5005.5,5030.5
Exp/Cntr=0.3,0.1

Type RM Length L Ch R = 1,27725,546,546,546
BEGIN DESCRIPTION:
North Fork Guadalupe River 49.0
END DESCRIPTION:
XS GIS Cut Line= 4
      1775371.26     13940176.32      1775336.66     13939513.79
      1775125.00     13939175.00      1774925.01     13938825.02
#Sta/Elev= 30
  3932.7 2167.01  3958.0 2166.16  3994.1 2162.78  4064.2 2158.35  4149.0 2154.24
  4244.4 2146.39  4294.5 2143.81  4610.5 2140.38  4647.1 2139.40  4699.0 2137.41
  4712.6 2136.20  4762.7 2134.66  4778.0 2133.33  4893.6 2129.79  4914.8 2127.73
  4936.6 2127.27  4960.2 2124.40  4987.9 2123.76  4991.0 2120.86  4991.5 2120.36
  5015.6 2120.36  5016.1 2120.86  5018.6 2124.03  5025.1 2127.63  5030.9 2133.45
  5041.0 2139.01  5053.2 2142.54  5076.2 2144.95  5331.8 2155.54  5398.7 2157.02
#Mann=3,-1,0
  3932.7    0.07       0  4991.0    0.05       0  5016.1    0.07       0
Bank Sta=4991,5016.1
Exp/Cntr=0.3,0.1

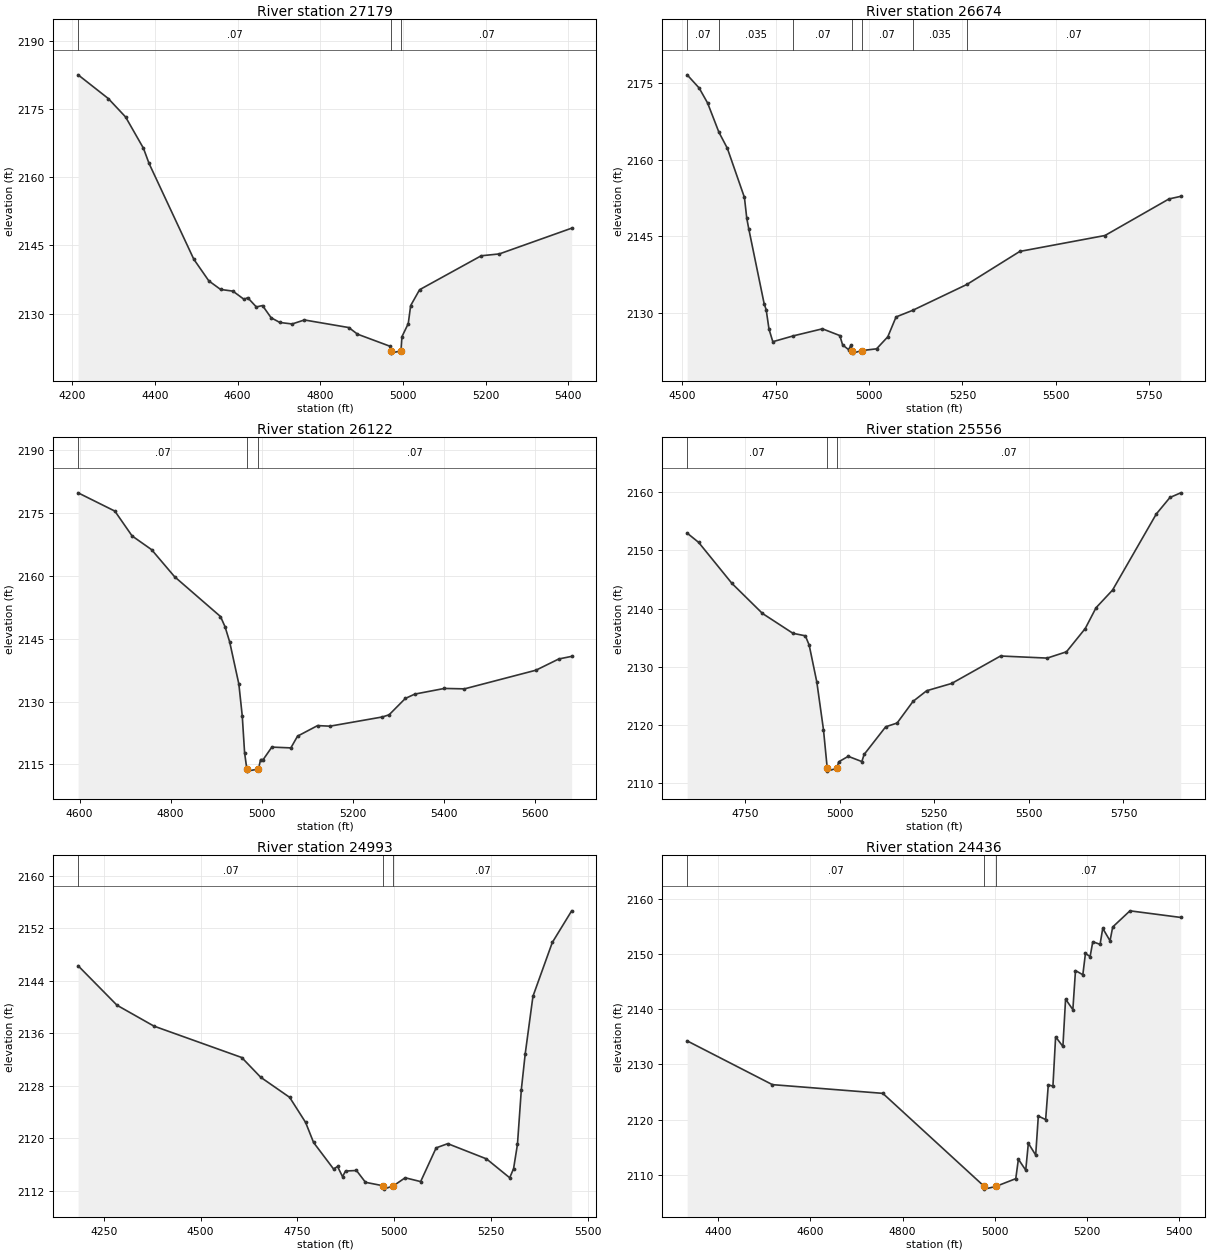
Type RM Length L Ch R = 1,27179,505,505,505
BEGIN DESCRIPTION:
North Fork Guadalupe River 48.0
END DESCRIPTION:
XS GIS Cut Line= 3
      1776225.01     13939375.01      1775575.00     13938925.00
      1775225.00     13938725.00
#Sta/Elev= 30
  4214.2 2182.47  4287.2 2177.26  4329.1 2173.20  4372.3 2166.32  4385.8 2162.99
  4494.0 2141.94  4530.4 2137.17  4558.8 2135.29  4588.6 2134.92  4615.6 2133.11
  4624.4 2133.48  4645.3 2131.44  4660.2 2131.75  4681.1 2129.06  4702.1 2128.03
  4731.8 2127.70  4761.5 2128.58  4869.0 2126.91  4889.9 2125.46  4968.3 2122.81
  4969.9 2121.79  4970.4 2121.29  4995.1 2121.79  4997.4 2124.90  5012.7 2127.79
  5018.5 2131.74  5040.1 2135.23  5189.1 2142.69  5233.0 2143.10  5407.9 2148.76
#Mann=3,-1,0
  4214.2    0.07       0  4969.9    0.05       0  4995.1    0.07       0
Bank Sta=4969.9,4995.1
Exp/Cntr=0.3,0.1

Type RM Length L Ch R = 1,26674,552,552,552
BEGIN DESCRIPTION:
North Fork Guadalupe River 47.0
END DESCRIPTION:
XS GIS Cut Line= 3
      1776225.00     13939275.00      1776025.00     13938825.00
      1775674.99     13938074.99
#Sta/Elev= 30
  4513.7 2176.58  4545.8 2174.00  4568.4 2171.07  4598.6 2165.37  4621.1 2162.24
  4666.9 2152.62  4673.1 2148.57  4678.5 2146.48  4719.6 2131.87  4725.0 2130.70
  4732.6 2126.90  4742.8 2124.44  4798.0 2125.59  4875.5 2126.96  4922.0 2125.64
  4929.5 2123.81  4945.3 2122.90  4951.4 2123.71  4955.8 2122.71  4956.3 2122.21
  4981.2 2122.71  5020.3 2123.05  5050.3 2125.40  5072.4 2129.28  5116.8 2130.57
  5262.2 2135.64  5403.4 2142.08  5631.2 2145.19  5802.3 2152.33  5833.8 2152.84
#Mann=7,-1,0
  4513.7    0.07       0  4598.6   0.035       0  4798.0    0.07       0
  4955.8    0.05       0  4981.2    0.07       0  5116.8   0.035       0
  5262.2    0.07       0
Bank Sta=4955.8,4981.2
Exp/Cntr=0.3,0.1

Type RM Length L Ch R = 1,26122,566,566,566
BEGIN DESCRIPTION:
North Fork Guadalupe River 46.0
END DESCRIPTION:
XS GIS Cut Line= 3
      1776575.01     13939175.04      1776525.00     13938775.00
      1775975.02     13938375.02
#Sta/Elev= 30
  4596.9 2179.77  4677.6 2175.41  4715.4 2169.49  4758.2 2166.22  4808.6 2159.77
  4909.4 2150.27  4919.4 2147.83  4929.5 2144.24  4949.7 2134.17  4957.2 2126.53
  4962.3 2117.78  4967.2 2113.90  4967.7 2113.40  4992.6 2113.90  4997.5 2116.16
  5003.1 2116.16  5022.1 2119.13  5063.8 2118.94  5078.5 2121.74  5122.5 2124.26
  5149.6 2124.12  5264.7 2126.32  5279.4 2126.83  5315.0 2130.73  5335.8 2131.77
  5400.8 2133.12  5444.8 2133.02  5601.7 2137.47  5651.9 2140.15  5680.1 2140.77
#Mann=3,-1,0
  4596.9    0.07       0  4967.2    0.05       0  4992.6    0.07       0
Bank Sta=4967.2,4992.6
Exp/Cntr=0.3,0.1

Type RM Length L Ch R = 1,25556,563,563,563
BEGIN DESCRIPTION:
North Fork Guadalupe River 45.0
END DESCRIPTION:
XS GIS Cut Line= 3
      1776975.00     13938775.01      1776925.00     13938375.00
      1776425.01     13937625.01
#Sta/Elev= 30
  4596.9 2152.95  4627.1 2151.37  4715.3 2144.32  4795.9 2139.17  4876.6 2135.76
  4909.3 2135.33  4919.4 2133.74  4939.6 2127.40  4957.2 2119.22  4967.1 2112.62
  4967.6 2112.12  4992.6 2112.62  4997.5 2113.72  5022.6 2114.66  5058.6 2113.76
  5064.6 2114.98  5121.7 2119.73  5151.8 2120.37  5193.8 2124.08  5229.9 2125.91
  5296.0 2127.16  5425.2 2131.87  5548.4 2131.51  5599.4 2132.59  5649.0 2136.58
  5677.6 2140.15  5721.1 2143.17  5836.8 2156.23  5872.9 2159.06  5901.4 2159.86
#Mann=3,-1,0
  4596.9    0.07       0  4967.1    0.05       0  4992.6    0.07       0
Bank Sta=4967.1,4992.6
Exp/Cntr=0.3,0.1

Type RM Length L Ch R = 1,24993,557,557,557
BEGIN DESCRIPTION:
North Fork Guadalupe River 44.0
END DESCRIPTION:
XS GIS Cut Line= 3
      1777324.99     13938674.98      1777125.00     13937875.00
      1777125.00     13937425.00
#Sta/Elev= 30
  4183.8 2146.32  4284.3 2140.30  4379.6 2137.12  4606.4 2132.33  4655.4 2129.32
  4730.1 2126.26  4771.3 2122.44  4791.9 2119.38  4843.5 2115.34  4853.8 2115.72
  4866.7 2114.17  4874.4 2115.03  4902.7 2115.11  4925.9 2113.31  4972.4 2112.77
  4972.9 2112.27  4998.0 2112.77  5028.4 2114.00  5068.4 2113.42  5108.4 2118.56
  5138.4 2119.20  5238.4 2116.88  5298.4 2114.00  5308.4 2115.40  5318.4 2119.10
  5328.4 2127.44  5338.4 2132.88  5358.4 2141.66  5408.4 2149.87  5458.4 2154.69
#Mann=3,-1,0
  4183.8    0.07       0  4972.4    0.05       0  4998.0    0.07       0
Bank Sta=4972.4,4998
Exp/Cntr=0.3,0.1

Type RM Length L Ch R = 1,24436,546,546,546
BEGIN DESCRIPTION:
North Fork Guadalupe River 43.0
END DESCRIPTION:
XS GIS Cut Line= 3
      1777424.99     13938275.04      1777575.00     13937625.00
      1777225.03     13937425.02
#Sta/Elev= 30
  4332.7 2134.27  4517.5 2126.33  4756.9 2124.75  4976.8 2107.87  4977.3 2107.37
  5002.4 2107.87  5045.2 2109.27  5050.9 2112.80  5066.8 2110.81  5072.5 2115.70
  5088.4 2113.55  5094.1 2120.63  5110.0 2119.99  5115.7 2126.26  5125.8 2126.08
  5131.6 2135.01  5147.4 2133.26  5153.2 2141.85  5169.0 2139.94  5174.7 2147.03
  5190.6 2146.27  5196.3 2150.14  5206.4 2149.56  5212.2 2152.26  5228.0 2151.79
  5233.8 2154.69  5249.6 2152.43  5255.4 2154.94  5292.8 2157.87  5402.9 2156.67
#Mann=3,-1,0
  4332.7    0.07       0  4976.8    0.05       0  5002.4    0.07       0
Bank Sta=4976.8,5002.4
Exp/Cntr=0.3,0.1

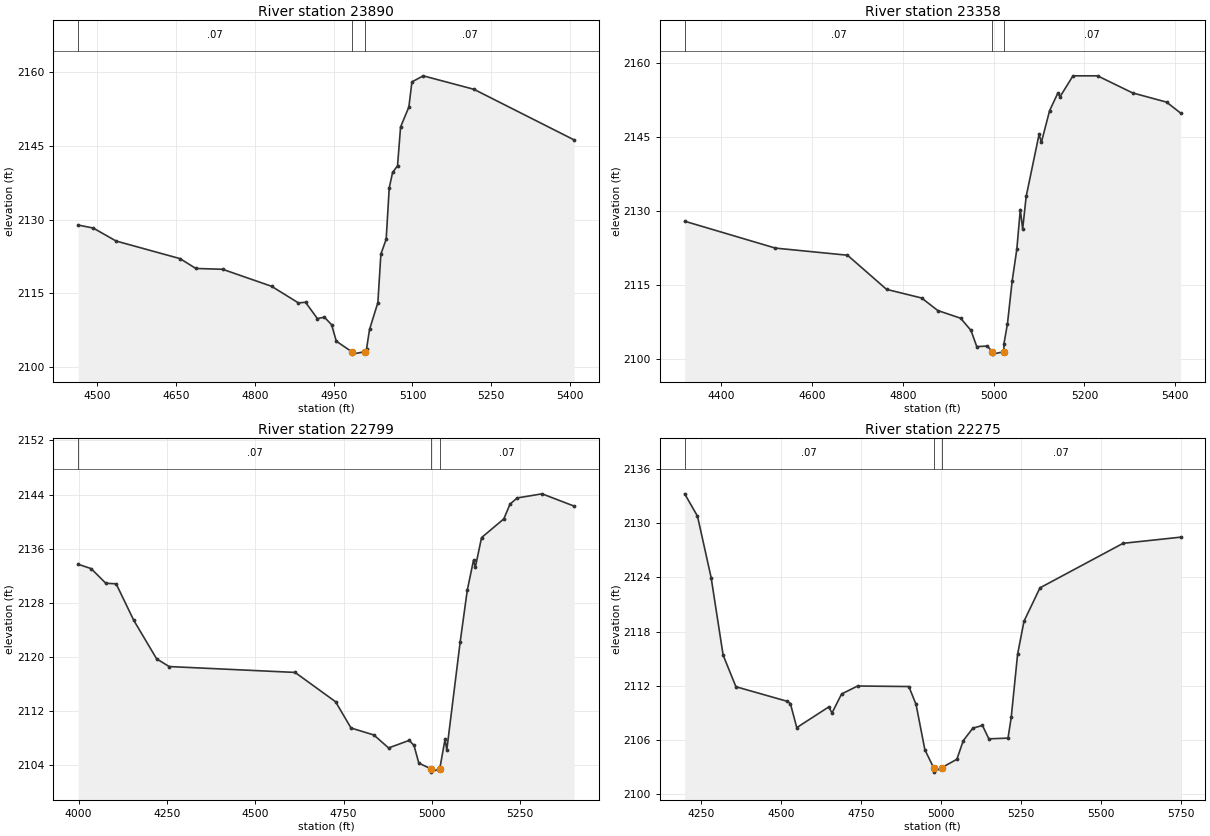
Type RM Length L Ch R = 1,23890,532,532,532
BEGIN DESCRIPTION:
North Fork Guadalupe River 42.0
END DESCRIPTION:
XS GIS Cut Line= 3
      1777774.99     13938225.02      1778075.00     13937775.00
      1778425.03     13937574.98
#Sta/Elev= 30
  4463.8 2128.88  4492.4 2128.27  4535.9 2125.63  4657.6 2122.05  4687.7 2120.05
  4738.7 2119.88  4831.9 2116.42  4883.0 2113.04  4896.5 2113.17  4919.0 2109.86
  4932.5 2110.13  4946.1 2108.60  4955.1 2105.25  4984.3 2103.12  4984.8 2102.62
  5009.9 2103.12  5012.6 2103.66  5018.3 2107.64  5034.2 2113.10  5039.9 2122.97
  5050.0 2125.99  5055.8 2136.43  5062.2 2139.58  5071.6 2140.93  5077.4 2148.83
  5093.2 2152.90  5099.0 2158.00  5120.5 2159.24  5217.0 2156.50  5407.8 2146.20
#Mann=3,-1,0
  4463.8    0.07       0  4984.3    0.05       0  5009.9    0.07       0
Bank Sta=4984.3,5009.9
Exp/Cntr=0.3,0.1

Type RM Length L Ch R = 1,23358,559,559,559
BEGIN DESCRIPTION:
North Fork Guadalupe River 41.0
END DESCRIPTION:
XS GIS Cut Line= 3
      1777975.01     13938424.99      1778525.00     13938025.00
      1778424.99     13937624.97
#Sta/Elev= 30
  4319.5 2127.92  4519.3 2122.48  4678.1 2121.04  4764.2 2114.13  4841.5 2112.38
  4877.1 2109.84  4927.3 2108.29  4950.1 2105.82  4962.9 2102.54  4986.0 2102.65
  4997.1 2101.52  4997.6 2101.02  5022.7 2101.52  5022.8 2103.13  5030.5 2107.18
  5040.8 2115.78  5051.1 2122.25  5058.8 2130.29  5064.0 2126.34  5071.7 2132.93
  5100.1 2145.50  5105.2 2143.89  5123.3 2150.30  5141.3 2153.82  5146.4 2153.13
  5174.8 2157.35  5228.9 2157.35  5306.2 2153.89  5380.9 2152.03  5411.9 2149.81
#Mann=3,-1,0
  4319.5    0.07       0  4997.1    0.05       0  5022.7    0.07       0
Bank Sta=4997.1,5022.7
Exp/Cntr=0.3,0.1

Type RM Length L Ch R = 1,22799,524,524,524
BEGIN DESCRIPTION:
North Fork Guadalupe River 40.0
END DESCRIPTION:
XS GIS Cut Line= 3
      1778174.99     13938925.01      1778975.00     13938325.00
      1778925.00     13937925.03
#Sta/Elev= 30
  3999.1 2133.67  4035.6 2133.03  4077.2 2130.86  4106.4 2130.78  4156.4 2125.36
  4221.0 2119.67  4256.4 2118.53  4612.7 2117.66  4727.2 2113.32  4771.0 2109.43
  4835.6 2108.40  4877.2 2106.48  4935.6 2107.60  4949.1 2106.85  4962.7 2104.24
  4996.3 2103.40  4996.8 2102.90  5022.0 2103.40  5036.9 2107.75  5041.9 2106.19
  5079.7 2122.16  5099.9 2129.85  5117.5 2134.27  5122.6 2133.22  5140.2 2137.62
  5203.2 2140.39  5220.8 2142.58  5241.0 2143.49  5311.5 2144.10  5402.2 2142.28
#Mann=3,-1,0
  3999.1    0.07       0  4996.3    0.05       0  5022.0    0.07       0
Bank Sta=4996.3,5022
Exp/Cntr=0.3,0.1

Type RM Length L Ch R = 1,22275,537,537,537
BEGIN DESCRIPTION:
North Fork Guadalupe River 39.0
END DESCRIPTION:
XS GIS Cut Line= 3
      1779225.00     13939475.02      1779275.00     13938675.00
      1779275.00     13937924.98
#Sta/Elev= 30
  4198.4 2133.23  4238.5 2130.76  4281.1 2123.98  4318.7 2115.40  4358.7 2111.91
  4519.0 2110.30  4529.1 2110.05  4549.1 2107.39  4649.3 2109.68  4659.3 2109.01
  4689.4 2111.11  4739.5 2111.99  4899.8 2111.93  4922.3 2109.95  4949.9 2104.94
  4977.1 2102.97  4977.6 2102.47  5002.8 2102.97  5050.0 2103.89  5070.0 2105.95
  5100.0 2107.33  5130.0 2107.63  5150.0 2106.15  5210.0 2106.23  5220.0 2108.51
  5240.0 2115.50  5260.0 2119.15  5310.0 2122.84  5570.0 2127.76  5750.0 2128.44
#Mann=3,-1,0
  4198.4    0.07       0  4977.1    0.05       0  5002.8    0.07       0
Bank Sta=4977.1,5002.8
Exp/Cntr=0.3,0.1