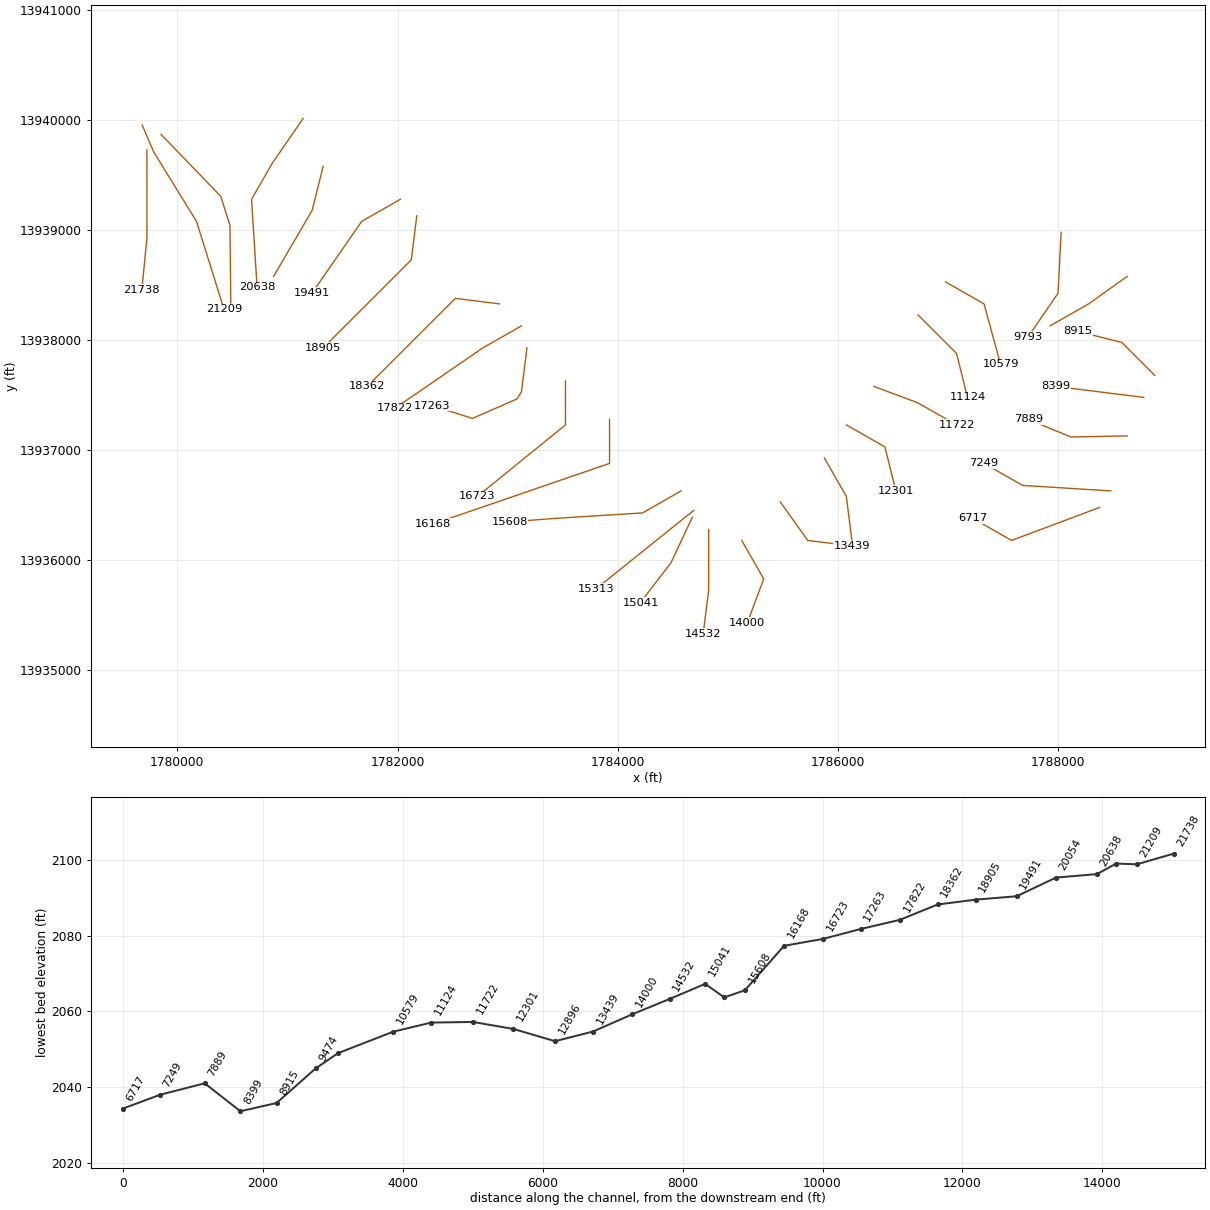
HEC-RAS study North Fork Guadalupe River.prj: North Fork Guadalupe River Base Level Engineering

--- North Fork Guadalupe River.g01 (geometry) --- (continued)

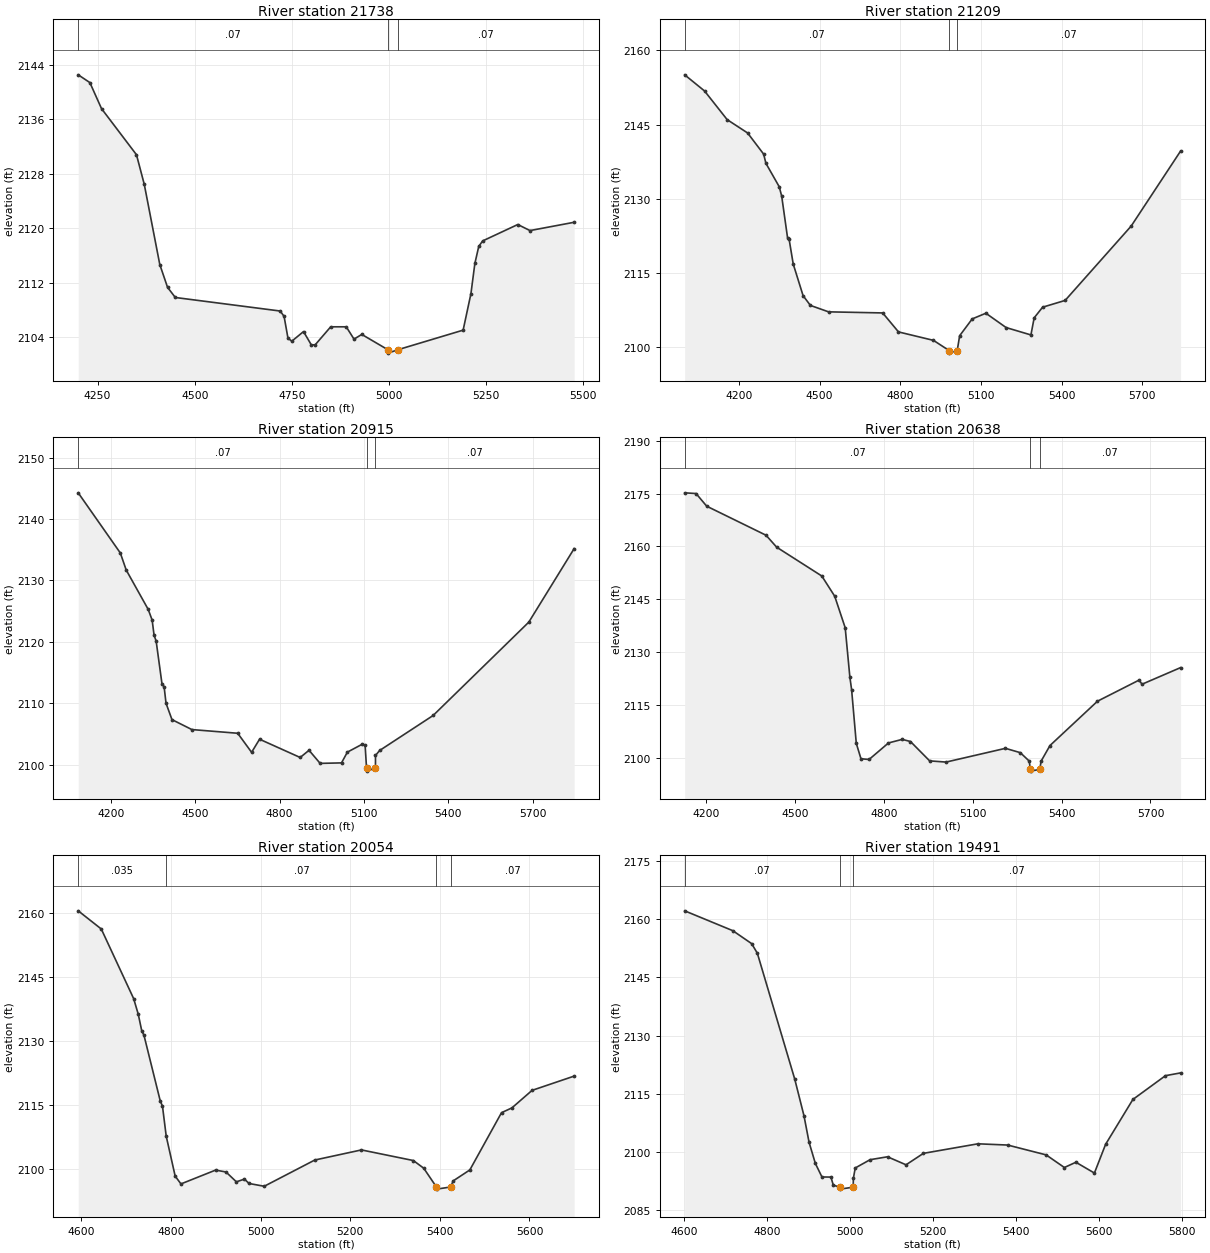
Type RM Length L Ch R = 1,21738,529,529,529
BEGIN DESCRIPTION:
North Fork Guadalupe River 38.0
END DESCRIPTION:
XS GIS Cut Line= 3
      1779725.00     13939725.03      1779725.00     13938925.00
      1779678.57     13938450.59
#Sta/Elev= 30
  4200.1 2142.54  4230.1 2141.40  4260.1 2137.57  4350.1 2130.79  4370.1 2126.45
  4410.1 2114.65  4430.1 2111.29  4450.1 2109.80  4720.1 2107.81  4730.1 2107.02
  4740.1 2103.81  4750.1 2103.38  4780.1 2104.79  4800.1 2102.84  4810.1 2102.84
  4850.1 2105.49  4890.1 2105.49  4910.1 2103.68  4930.1 2104.37  4997.3 2102.12
  4997.8 2101.62  5023.0 2102.12  5191.0 2105.00  5211.1 2110.37  5221.2 2114.80
  5231.2 2117.31  5241.3 2118.12  5331.7 2120.53  5363.1 2119.64  5476.8 2120.86
#Mann=3,-1,0
  4200.1    0.07       0  4997.3    0.05       0  5023.0    0.07       0
Bank Sta=4997.3,5023
Exp/Cntr=0.3,0.1

Type RM Length L Ch R = 1,21209,294,294,294
BEGIN DESCRIPTION:
North Fork Guadalupe River 37.0
END DESCRIPTION:
XS GIS Cut Line= 4
      1779681.86     13939950.23      1779785.58     13939707.81
      1780175.00     13939075.00      1780425.01     13938274.96
#Sta/Elev= 30
  3997.9 2155.07  4071.9 2151.80  4155.9 2146.01  4232.0 2143.31  4291.7 2139.03
  4300.1 2137.17  4349.6 2132.44  4358.8 2130.53  4380.5 2122.15  4386.3 2121.84
  4401.7 2116.80  4438.4 2110.40  4465.6 2108.43  4533.1 2107.13  4734.5 2106.91
  4793.3 2103.07  4923.5 2101.36  4982.2 2099.28  4982.7 2098.78  5011.7 2099.28
  5020.8 2102.30  5067.5 2105.70  5118.3 2106.85  5193.7 2103.95  5285.9 2102.46
  5298.0 2105.92  5329.4 2108.07  5413.2 2109.44  5658.9 2124.48  5842.8 2139.66
#Mann=3,-1,0
  3997.9    0.07       0  4982.2    0.05       0  5011.7    0.07       0
Bank Sta=4982.2,5011.7
Exp/Cntr=0.3,0.1

Type RM Length L Ch R = 1,20915,277,277,277
BEGIN DESCRIPTION:
Mapping XS acee1881
END DESCRIPTION:
XS GIS Cut Line= 4
      1779853.68     13939865.04      1780395.32     13939302.57
      1780478.66     13939039.55      1780486.47     13938333.87
#Sta/Elev= 30
  4084.5 2144.26  4234.1 2134.48  4255.1 2131.70  4333.1 2125.31  4347.2 2123.57
  4354.2 2121.07  4361.4 2120.17  4382.5 2113.09  4389.7 2112.75  4396.6 2110.03
  4417.7 2107.37  4488.5 2105.75  4651.3 2105.15  4700.7 2102.05  4729.0 2104.18
  4873.3 2101.21  4904.8 2102.38  4944.3 2100.25  5020.2 2100.33  5041.1 2102.08
  5093.6 2103.36  5104.1 2103.19  5109.2 2099.49  5109.7 2098.99  5140.9 2099.49
  5141.0 2101.54  5155.8 2102.35  5345.8 2108.04  5685.9 2123.23  5847.0 2135.19
#Mann=3,-1,0
  4084.5    0.07       0  5109.2    0.05       0  5140.9    0.07       0
Bank Sta=5109.2,5140.9
Exp/Cntr=0.3,0.1

Type RM Length L Ch R = 1,20638,584,584,584
BEGIN DESCRIPTION:
North Fork Guadalupe River 36.0
END DESCRIPTION:
XS GIS Cut Line= 4
      1781142.78     13940010.15      1780857.95     13939595.16
      1780675.00     13939275.00      1780725.00     13938475.04
#Sta/Elev= 30
  4128.1 2175.20  4166.5 2175.00  4202.4 2171.41  4402.7 2163.16  4438.5 2159.77
  4590.8 2151.59  4634.4 2145.85  4669.8 2136.89  4685.6 2122.84  4691.4 2119.34
  4707.2 2104.09  4723.0 2099.71  4750.4 2099.51  4815.9 2104.20  4862.0 2105.21
  4890.0 2104.61  4954.8 2099.11  5010.2 2098.77  5210.6 2102.67  5260.7 2101.44
  5290.7 2099.06  5294.9 2096.70  5295.4 2096.20  5326.6 2096.70  5330.8 2099.02
  5360.9 2103.47  5521.2 2116.05  5661.5 2122.04  5671.5 2120.87  5801.7 2125.59
#Mann=3,-1,0
  4128.1    0.07       0  5294.9    0.05       0  5326.6    0.07       0
Bank Sta=5294.9,5326.6
Exp/Cntr=0.3,0.1

Type RM Length L Ch R = 1,20054,563,563,563
BEGIN DESCRIPTION:
North Fork Guadalupe River 35.0
END DESCRIPTION:
XS GIS Cut Line= 3
      1781324.99     13939574.96      1781225.00     13939175.00
      1780875.00     13938574.99
#Sta/Elev= 30
  4592.8 2160.52  4644.3 2156.26  4716.5 2139.95  4726.8 2136.29  4734.5 2132.45
  4739.6 2131.34  4775.7 2116.05  4780.9 2114.71  4789.2 2107.71  4809.2 2098.34
  4822.1 2096.51  4899.4 2099.75  4922.6 2099.31  4945.8 2097.00  4963.8 2097.64
  4974.1 2096.61  5008.0 2095.96  5120.8 2102.11  5225.0 2104.48  5340.8 2101.99
  5364.0 2100.19  5392.3 2095.79  5392.8 2095.29  5424.0 2095.79  5429.7 2097.22
  5466.9 2099.79  5537.6 2113.21  5560.8 2114.33  5605.8 2118.44  5699.7 2121.78
#Mann=4,-1,0
  4592.8   0.035       0  4789.2    0.07       0  5392.3    0.05       0
  5424.0    0.07       0
Bank Sta=5392.3,5424
Exp/Cntr=0.3,0.1

Type RM Length L Ch R = 1,19491,586,586,586
BEGIN DESCRIPTION:
North Fork Guadalupe River 34.0
END DESCRIPTION:
XS GIS Cut Line= 3
      1782024.97     13939274.99      1781675.00     13939075.00
      1781224.97     13938424.96
#Sta/Elev= 30
  4602.1 2162.21  4718.0 2157.08  4763.3 2153.74  4777.0 2151.26  4867.0 2118.77
  4889.3 2109.28  4901.5 2102.45  4916.6 2097.00  4932.5 2093.50  4954.1 2093.47
  4959.8 2091.40  4975.4 2090.86  4975.9 2090.36  5007.6 2090.86  5008.2 2093.17
  5012.6 2095.82  5048.4 2097.96  5090.3 2098.71  5134.9 2096.64  5176.8 2099.60
  5307.9 2102.06  5379.5 2101.74  5472.1 2099.20  5516.0 2095.94  5543.7 2097.30
  5588.3 2094.51  5615.3 2101.94  5680.9 2113.51  5759.3 2119.65  5795.8 2120.37
#Mann=3,-1,0
  4602.1    0.07       0  4975.4    0.05       0  5007.6    0.07       0
Bank Sta=4975.4,5007.6
Exp/Cntr=0.3,0.1

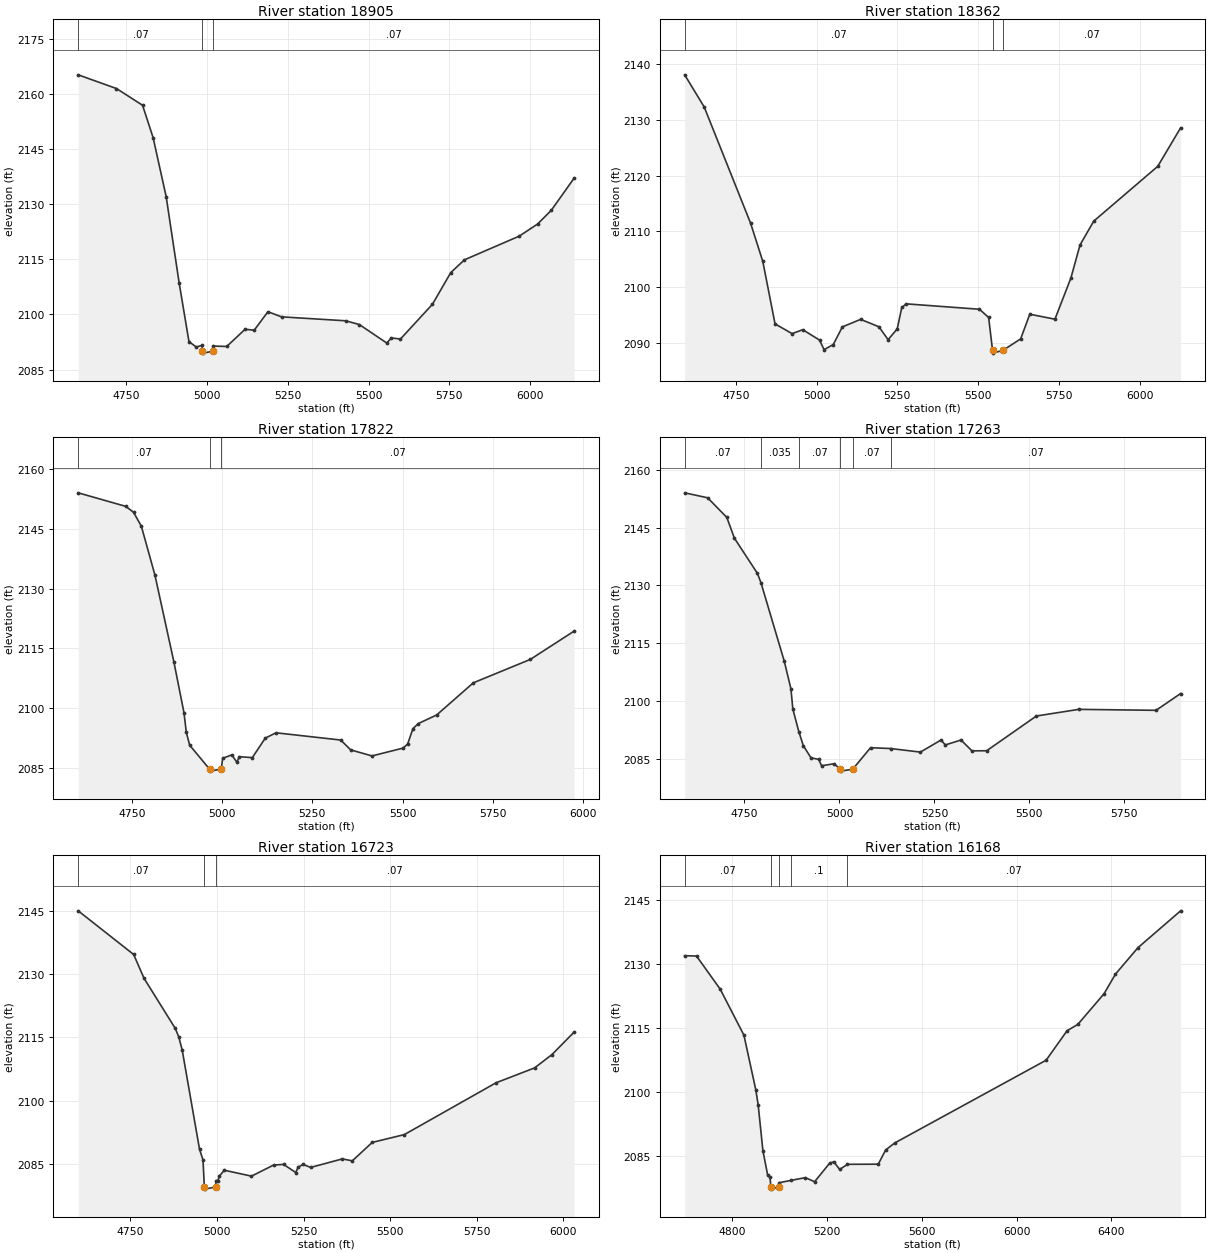
Type RM Length L Ch R = 1,18905,543,543,543
BEGIN DESCRIPTION:
North Fork Guadalupe River 33.0
END DESCRIPTION:
XS GIS Cut Line= 3
      1782175.00     13939125.02      1782125.00     13938725.00
      1781325.00     13937925.00
#Sta/Elev= 30
  4601.4 2165.19  4719.8 2161.46  4800.5 2156.91  4833.2 2148.08  4873.5 2132.07
  4913.8 2108.53  4944.1 2092.59  4966.7 2091.14  4984.4 2091.57  4985.9 2089.97
  4986.4 2089.47  5018.1 2089.97  5018.7 2091.39  5061.1 2091.29  5117.7 2095.96
  5146.0 2095.71  5188.4 2100.73  5230.8 2099.34  5428.8 2098.27  5471.2 2097.25
  5556.1 2092.22  5570.2 2093.60  5598.5 2093.31  5697.5 2102.77  5754.1 2111.38
  5796.5 2114.86  5966.2 2121.31  6022.8 2124.60  6065.2 2128.33  6135.9 2137.10
#Mann=3,-1,0
  4601.4    0.07       0  4985.9    0.05       0  5018.1    0.07       0
Bank Sta=4985.9,5018.1
Exp/Cntr=0.3,0.1

Type RM Length L Ch R = 1,18362,540,540,540
BEGIN DESCRIPTION:
North Fork Guadalupe River 32.0
END DESCRIPTION:
XS GIS Cut Line= 3
      1782924.98     13938325.00      1782525.00     13938375.00
      1781724.97     13937574.97
#Sta/Elev= 30
  4592.1 2138.06  4652.5 2132.30  4796.2 2111.45  4833.9 2104.61  4871.7 2093.43
  4924.6 2091.68  4957.4 2092.39  5009.3 2090.53  5023.5 2088.81  5051.8 2089.73
  5080.0 2092.89  5136.6 2094.24  5193.2 2092.91  5221.5 2090.60  5249.7 2092.53
  5263.9 2096.38  5278.0 2097.02  5504.3 2096.05  5532.6 2094.58  5544.7 2088.69
  5545.3 2088.19  5577.0 2088.69  5631.6 2090.74  5659.9 2095.16  5737.7 2094.27
  5787.1 2101.65  5815.4 2107.58  5857.9 2111.85  6055.8 2121.66  6126.6 2128.56
#Mann=3,-1,0
  4592.1    0.07       0  5544.7    0.05       0  5577.0    0.07       0
Bank Sta=5544.7,5577
Exp/Cntr=0.3,0.1

Type RM Length L Ch R = 1,17822,559,559,559
BEGIN DESCRIPTION:
North Fork Guadalupe River 31.0
END DESCRIPTION:
XS GIS Cut Line= 3
      1783125.00     13938125.00      1782775.00     13937925.00
      1781975.03     13937375.02
#Sta/Elev= 30
  4601.5 2154.05  4733.2 2150.65  4754.8 2149.16  4776.4 2145.66  4813.9 2133.43
  4866.4 2111.65  4894.5 2098.81  4901.0 2093.87  4910.3 2090.65  4965.4 2084.64
  4965.9 2084.14  4997.7 2084.64  5001.7 2087.36  5026.9 2088.22  5041.0 2086.38
  5047.9 2087.77  5083.8 2087.53  5119.6 2092.42  5149.4 2093.77  5328.7 2091.95
  5356.5 2089.47  5415.3 2087.96  5501.9 2089.93  5514.3 2091.00  5528.9 2094.83
  5543.8 2096.09  5594.6 2098.25  5696.0 2106.32  5854.1 2112.21  5975.4 2119.32
#Mann=3,-1,0
  4601.5    0.07       0  4965.4    0.05       0  4997.7    0.07       0
Bank Sta=4965.4,4997.7
Exp/Cntr=0.3,0.1

Type RM Length L Ch R = 1,17263,540,540,540
BEGIN DESCRIPTION:
North Fork Guadalupe River 30.0
END DESCRIPTION:
XS GIS Cut Line= 5
      1783175.00     13937924.99      1783125.00     13937525.00
      1783085.20     13937461.31      1782680.30     13937283.93
      1782313.34     13937401.20
#Sta/Elev= 30
  4592.6 2154.09  4653.1 2152.80  4703.5 2147.70  4723.6 2142.28  4784.1 2133.15
  4793.5 2130.69  4854.6 2110.37  4872.3 2103.14  4877.3 2097.87  4893.1 2091.99
  4905.0 2088.33  4925.2 2085.17  4945.3 2084.80  4952.9 2083.13  4985.6 2083.64
  5002.6 2082.23  5003.1 2081.73  5034.9 2082.23  5081.9 2087.82  5135.2 2087.60
  5213.0 2086.68  5267.5 2089.82  5278.7 2088.54  5320.0 2089.82  5348.8 2087.00
  5387.6 2087.03  5518.4 2096.06  5630.0 2097.79  5833.5 2097.54  5898.1 2101.91
#Mann=6,-1,0
  4592.6    0.07       0  4793.5   0.035       0  4893.1    0.07       0
  5002.6    0.05       0  5034.9    0.07       0  5135.2    0.07       0
Bank Sta=5002.6,5034.9
Exp/Cntr=0.3,0.1

Type RM Length L Ch R = 1,16723,555,555,555
BEGIN DESCRIPTION:
North Fork Guadalupe River 29.0
END DESCRIPTION:
XS GIS Cut Line= 3
      1783525.00     13937625.00      1783525.00     13937225.00
      1782724.98     13936574.99
#Sta/Elev= 30
  4600.0 2144.94  4760.0 2134.61  4790.0 2128.96  4880.0 2117.13  4890.0 2115.14
  4900.0 2112.01  4950.0 2088.54  4960.0 2086.02  4963.9 2079.61  4964.4 2079.11
  4996.2 2079.61  4997.5 2081.12  5003.2 2081.12  5007.2 2082.20  5021.6 2083.58
  5099.9 2082.18  5163.8 2084.81  5192.5 2084.95  5227.7 2083.04  5234.2 2084.27
  5248.5 2084.96  5270.6 2084.24  5362.0 2086.26  5390.8 2085.80  5448.2 2090.16
  5540.9 2092.01  5805.3 2104.26  5916.5 2107.78  5966.4 2110.91  6030.8 2116.26
#Mann=3,-1,0
  4600.0    0.07       0  4963.9    0.05       0  4996.2    0.07       0
Bank Sta=4963.9,4996.2
Exp/Cntr=0.3,0.1

Type RM Length L Ch R = 1,16168,560,560,560
BEGIN DESCRIPTION:
North Fork Guadalupe River 28.0
END DESCRIPTION:
XS GIS Cut Line= 3
      1783925.00     13937275.00      1783925.00     13936875.00
      1782324.99     13936325.00
#Sta/Elev= 30
  4600.3 2131.96  4650.3 2131.87  4750.3 2124.11  4850.3 2113.33  4900.3 2100.54
  4910.3 2097.02  4930.3 2086.29  4950.3 2080.61  4960.3 2080.03  4964.1 2077.80
  4964.6 2077.30  4996.4 2077.80  4997.8 2078.79  5047.4 2079.33  5109.6 2079.99
  5148.3 2079.03  5211.8 2083.37  5229.3 2083.71  5254.1 2081.91  5286.9 2083.11
  5416.8 2083.14  5448.0 2086.47  5486.7 2088.12  6124.8 2107.48  6213.2 2114.38
  6258.6 2115.87  6369.4 2123.05  6417.3 2127.64  6512.4 2133.84  6692.2 2142.46
#Mann=5,-1,0
  4600.3    0.07       0  4964.1    0.05       0  4996.4    0.07       0
  5047.4     0.1       0  5286.9    0.07       0
Bank Sta=4964.1,4996.4
Exp/Cntr=0.3,0.1

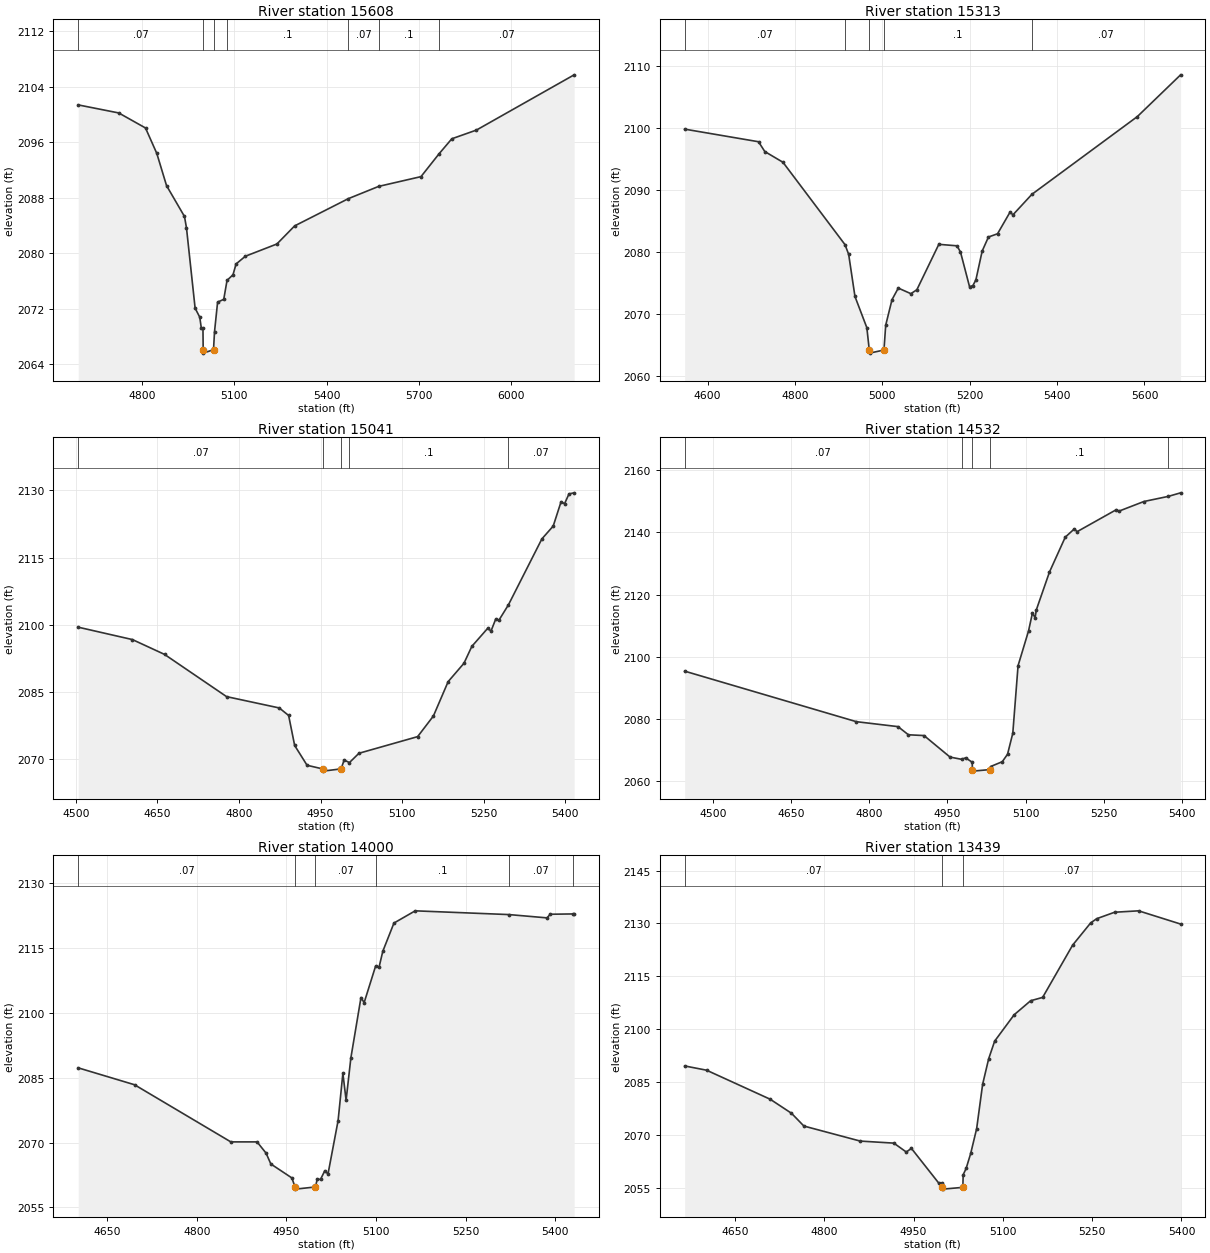
Type RM Length L Ch R = 1,15608,295,295,295
BEGIN DESCRIPTION:
North Fork Guadalupe River 27.0
END DESCRIPTION:
XS GIS Cut Line= 4
      1784574.99     13936624.99      1784225.00     13936425.00
      1783425.00     13936375.00      1783018.37     13936343.62
#Sta/Elev= 30
  4592.3 2101.40  4724.0 2100.24  4811.1 2098.07  4847.8 2094.40  4879.5 2089.75
  4937.8 2085.30  4944.3 2083.66  4972.4 2072.07  4987.5 2070.76  4992.5 2069.21
  4997.9 2069.21  4998.6 2066.08  4999.2 2065.58  5032.2 2066.08  5035.5 2068.67
  5045.5 2072.94  5065.5 2073.34  5076.2 2076.08  5095.6 2076.89  5105.6 2078.45
  5135.7 2079.56  5238.4 2081.33  5296.0 2083.94  5470.5 2087.87  5569.1 2089.64
  5706.8 2091.05  5765.5 2094.34  5807.0 2096.51  5887.2 2097.77  6204.8 2105.74
#Mann=7,-1,0
  4592.3    0.07       0  4998.6    0.05       0  5032.2    0.07       0
  5076.2     0.1       0  5470.5    0.07       0  5569.1     0.1       0
  5765.5    0.07       0
Bank Sta=4998.6,5032.2
Exp/Cntr=0.3,0.1

Type RM Length L Ch R = 1,15313,272,272,272
BEGIN DESCRIPTION:
North Fork Guadalupe River 26.1
END DESCRIPTION:
XS GIS Cut Line= 2
      1784689.24     13936447.87      1783804.39     13935736.58
#Sta/Elev= 30
  4547.5 2099.78  4716.5 2097.75  4730.9 2096.17  4772.5 2094.44  4914.6 2081.16
  4922.9 2079.60  4937.3 2072.82  4964.5 2067.79  4970.1 2064.19  4970.7 2063.69
  5003.7 2064.19  5007.7 2068.19  5022.1 2072.30  5036.5 2074.17  5065.3 2073.27
  5079.0 2073.90  5129.3 2081.22  5170.9 2080.98  5178.9 2079.98  5199.7 2074.37
  5207.3 2074.58  5214.1 2075.48  5228.5 2080.13  5242.9 2082.40  5263.7 2082.92
  5292.5 2086.43  5298.9 2085.97  5342.4 2089.28  5583.7 2101.80  5682.8 2108.53
#Mann=5,-1,0
  4547.5    0.07       0  4914.6     0.1       0  4970.1    0.05       0
  5003.7     0.1       0  5342.4    0.07       0
Bank Sta=4970.1,5003.7
Exp/Cntr=0.3,0.1

Type RM Length L Ch R = 1,15041,509,509,509
BEGIN DESCRIPTION:
North Fork Guadalupe River 26.2
END DESCRIPTION:
XS GIS Cut Line= 3
      1784676.53     13936385.33      1784483.40     13935973.01
      1784205.64     13935610.62
#Sta/Elev= 30
  4504.3 2099.43  4604.0 2096.66  4663.0 2093.35  4777.1 2083.91  4874.0 2081.38
  4891.2 2079.70  4902.3 2072.99  4925.1 2068.57  4953.6 2067.76  4954.2 2067.26
  4987.6 2067.76  4993.3 2069.74  5003.0 2069.17  5020.5 2071.25  5128.4 2074.97
  5157.4 2079.58  5184.5 2087.26  5213.6 2091.37  5228.1 2095.15  5257.1 2099.16
  5263.4 2098.59  5271.7 2101.16  5278.0 2101.02  5295.3 2104.41  5356.9 2119.17
  5377.7 2122.03  5392.2 2127.49  5398.5 2127.01  5406.7 2129.22  5416.2 2129.46
#Mann=5,-1,0
  4504.3    0.07       0  4953.6    0.05       0  4987.6    0.07       0
  5003.0     0.1       0  5295.3    0.07       0
Bank Sta=4953.6,4987.6
Exp/Cntr=0.3,0.1

Type RM Length L Ch R = 1,14532,532,532,532
BEGIN DESCRIPTION:
North Fork Guadalupe River 26.0
END DESCRIPTION:
XS GIS Cut Line= 3
      1784825.00     13936274.97      1784825.00     13935725.00
      1784775.00     13935324.98
#Sta/Elev= 30
  4445.0 2095.41  4775.0 2079.17  4855.0 2077.58  4875.0 2074.96  4905.0 2074.71
  4955.0 2067.79  4977.1 2067.08  4985.0 2067.55  4997.5 2066.14  4998.1 2063.78
  4998.8 2063.28  5032.1 2063.78  5032.8 2064.75  5055.4 2066.31  5065.5 2068.72
  5075.6 2075.48  5085.7 2097.17  5105.8 2108.32  5113.4 2114.14  5118.4 2112.54
  5120.9 2115.15  5146.1 2127.28  5176.4 2138.47  5194.0 2141.15  5199.0 2140.22
  5274.6 2147.31  5279.7 2146.84  5327.5 2149.93  5374.5 2151.58  5398.1 2152.72
#Mann=5,-1,0
  4445.0    0.07       0  4977.1     0.1       0  4998.1    0.05       0
  5032.1     0.1       0  5374.5    0.07       0
Bank Sta=4998.1,5032.1
Exp/Cntr=0.3,0.1

Type RM Length L Ch R = 1,14000,561,561,561
BEGIN DESCRIPTION:
North Fork Guadalupe River 25.0
END DESCRIPTION:
XS GIS Cut Line= 3
      1785125.02     13936174.97      1785325.00     13935825.00
      1785174.99     13935424.98
#Sta/Elev= 30
  4601.5 2087.31  4695.8 2083.40  4857.0 2070.18  4900.9 2070.18  4916.0 2067.58
  4924.0 2065.07  4959.2 2061.84  4964.5 2059.75  4965.2 2059.25  4998.5 2059.75
  5001.7 2061.52  5007.2 2061.52  5014.4 2063.52  5019.7 2062.74  5036.6 2075.11
  5044.6 2086.04  5050.0 2079.83  5058.0 2089.63  5074.9 2103.58  5080.2 2102.40
  5099.3 2110.81  5105.1 2110.55  5111.4 2114.26  5130.1 2120.81  5165.7 2123.64
  5322.8 2122.77  5386.4 2122.01  5391.7 2122.85  5429.2 2122.92  5431.8 2122.93
#Mann=6,-1,0
  4601.5    0.07       0  4964.5    0.05       0  4998.5    0.07       0
  5099.3     0.1       0  5322.8    0.07       0  5429.2     0.1       0
Bank Sta=4964.5,4998.5
Exp/Cntr=0.3,0.1

Type RM Length L Ch R = 1,13439,543,543,543
BEGIN DESCRIPTION:
North Fork Guadalupe River 24.0
END DESCRIPTION:
XS GIS Cut Line= 3
      1785475.03     13936524.96      1785725.00     13936175.00
      1786125.02     13936125.00
#Sta/Elev= 30
  4565.4 2089.62  4602.2 2088.41  4709.1 2080.18  4744.8 2076.21  4765.7 2072.58
  4860.3 2068.32  4916.8 2067.74  4937.7 2065.22  4946.3 2066.25  4992.4 2056.38
  4998.0 2056.38  4998.5 2055.20  4999.2 2054.70  5032.7 2055.20  5033.3 2058.79
  5038.3 2060.58  5045.9 2064.80  5055.9 2071.82  5066.0 2084.45  5076.1 2091.64
  5086.2 2096.66  5118.9 2104.12  5146.6 2108.10  5166.8 2109.05  5217.2 2123.87
  5247.4 2130.15  5257.5 2131.35  5287.7 2133.19  5328.0 2133.59  5398.6 2129.84
#Mann=3,-1,0
  4565.4    0.07       0  4998.5    0.05       0  5032.7    0.07       0
Bank Sta=4998.5,5032.7
Exp/Cntr=0.3,0.1

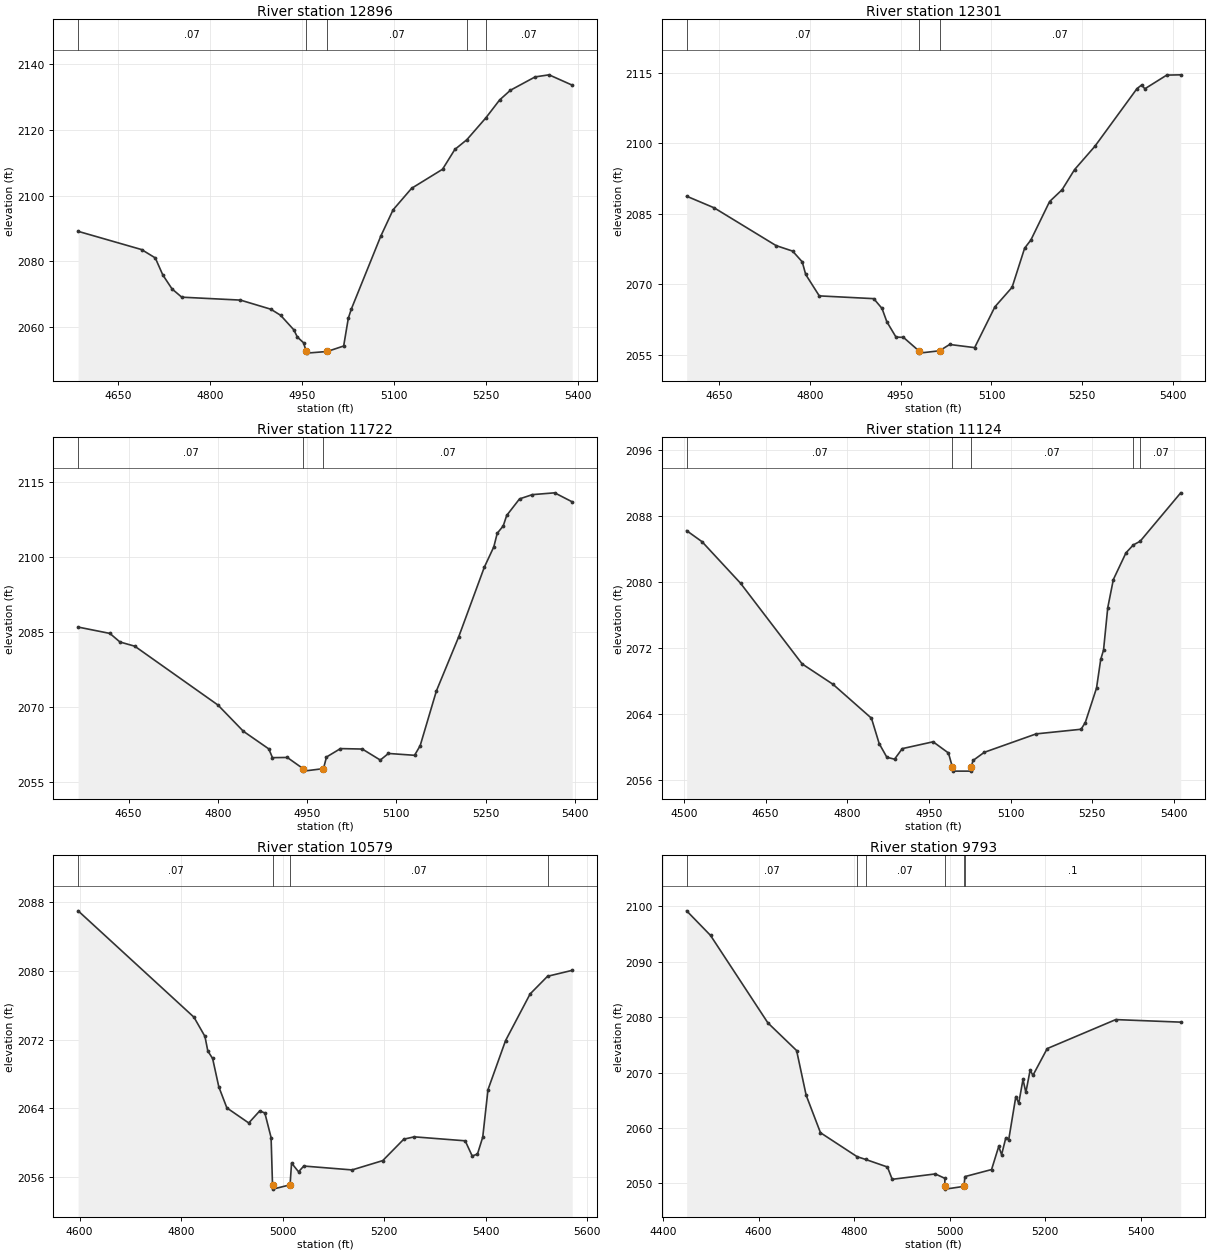
Type RM Length L Ch R = 1,12896,595,595,595
BEGIN DESCRIPTION:
North Fork Guadalupe River 23.0
END DESCRIPTION:
XS GIS Cut Line= 3
      1785875.02     13936924.97      1786075.00     13936575.00
      1786125.00     13936174.99
#Sta/Elev= 30
  4584.8 2089.12  4688.4 2083.58  4710.7 2081.05  4723.0 2075.87  4738.1 2071.62
  4753.9 2069.13  4849.7 2068.24  4899.3 2065.47  4915.2 2063.63  4936.8 2059.21
  4942.5 2057.03  4952.6 2055.29  4957.1 2052.64  4957.8 2052.14  4991.3 2052.64
  5018.1 2054.30  5025.7 2062.75  5030.7 2065.57  5078.6 2087.63  5098.7 2095.64
  5129.0 2102.19  5179.4 2107.96  5199.5 2113.98  5219.1 2116.94  5250.2 2123.59
  5272.6 2129.02  5290.2 2131.96  5330.5 2136.01  5353.2 2136.64  5391.0 2133.51
#Mann=5,-1,0
  4584.8    0.07       0  4957.1    0.05       0  4991.3    0.07       0
  5219.1     0.1       0  5250.2    0.07       0
Bank Sta=4957.1,4991.3
Exp/Cntr=0.3,0.1

Type RM Length L Ch R = 1,12301,579,579,579
BEGIN DESCRIPTION:
North Fork Guadalupe River 22.0
END DESCRIPTION:
XS GIS Cut Line= 3
      1786074.98     13937225.01      1786425.00     13937025.00
      1786524.99     13936625.05
#Sta/Elev= 30
  4596.9 2088.73  4642.3 2086.26  4744.5 2078.23  4771.8 2077.06  4787.7 2074.77
  4793.4 2072.09  4815.8 2067.54  4905.7 2066.95  4919.4 2064.86  4927.3 2062.04
  4942.4 2058.78  4954.7 2058.72  4980.0 2055.87  4980.7 2055.37  5014.3 2055.87
  5031.0 2057.21  5072.2 2056.54  5105.7 2065.22  5134.0 2069.36  5154.7 2077.68
  5165.0 2079.41  5195.9 2087.59  5216.5 2090.10  5237.1 2094.38  5270.6 2099.33
  5340.2 2111.61  5347.9 2112.37  5353.1 2111.56  5389.2 2114.47  5412.3 2114.53
#Mann=3,-1,0
  4596.9    0.07       0  4980.0    0.05       0  5014.3    0.07       0
Bank Sta=4980,5014.3
Exp/Cntr=0.3,0.1

Type RM Length L Ch R = 1,11722,598,598,598
BEGIN DESCRIPTION:
North Fork Guadalupe River 21.0
END DESCRIPTION:
XS GIS Cut Line= 3
      1786325.01     13937575.00      1786725.00     13937425.00
      1787075.00     13937225.00
#Sta/Elev= 30
  4565.1 2085.99  4618.5 2084.72  4635.4 2083.01  4660.3 2082.17  4800.1 2070.42
  4842.8 2065.18  4885.5 2061.66  4891.7 2059.91  4916.6 2059.95  4943.1 2057.72
  4943.8 2057.22  4977.4 2057.72  4982.5 2060.04  5006.0 2061.72  5042.7 2061.63
  5072.9 2059.43  5086.6 2060.75  5130.5 2060.38  5139.9 2062.30  5167.2 2073.24
  5204.6 2084.02  5247.8 2097.97  5263.7 2102.02  5269.4 2104.72  5279.5 2106.19
  5285.3 2108.28  5306.9 2111.59  5328.5 2112.44  5365.9 2112.80  5395.4 2111.00
#Mann=3,-1,0
  4565.1    0.07       0  4943.1    0.05       0  4977.4    0.07       0
Bank Sta=4943.1,4977.4
Exp/Cntr=0.3,0.1

Type RM Length L Ch R = 1,11124,545,545,545
BEGIN DESCRIPTION:
North Fork Guadalupe River 20.0
END DESCRIPTION:
XS GIS Cut Line= 3
      1786725.00     13938225.00      1787075.00     13937875.00
      1787175.00     13937474.99
#Sta/Elev= 30
  4505.0 2086.23  4533.3 2084.89  4604.0 2079.85  4717.1 2070.06  4773.7 2067.59
  4844.4 2063.47  4858.6 2060.39  4872.7 2058.73  4886.8 2058.50  4901.0 2059.78
  4957.6 2060.61  4985.8 2059.25  4993.0 2057.55  4993.7 2057.05  5026.9 2057.05
  5027.6 2057.55  5030.9 2058.34  5051.5 2059.33  5146.9 2061.57  5229.3 2062.13
  5237.1 2062.95  5257.7 2067.13  5265.4 2070.60  5270.6 2071.75  5278.3 2076.87
  5288.6 2080.30  5311.8 2083.54  5325.3 2084.50  5337.8 2084.94  5412.3 2090.82
#Mann=5,-1,0
  4505.0    0.07       0  4993.0    0.05       0  5027.6    0.07       0
  5325.3     0.1       0  5337.8    0.07       0
Bank Sta=4993,5027.6
Exp/Cntr=0.3,0.1

Type RM Length L Ch R = 1,10579,786,786,786
BEGIN DESCRIPTION:
North Fork Guadalupe River 19.0
END DESCRIPTION:
XS GIS Cut Line= 3
      1786975.02     13938524.99      1787325.00     13938325.00
      1787475.01     13937774.98
#Sta/Elev= 30
  4597.2 2086.94  4825.4 2074.59  4847.0 2072.36  4852.7 2070.66  4862.1 2069.80
  4874.3 2066.51  4890.2 2064.06  4933.3 2062.31  4954.9 2063.71  4965.0 2063.47
  4977.3 2060.62  4980.1 2055.13  4980.8 2054.63  5014.7 2055.13  5017.6 2057.66
  5031.4 2056.64  5041.7 2057.31  5136.8 2056.86  5197.2 2057.94  5238.7 2060.43
  5259.4 2060.70  5359.6 2060.24  5373.4 2058.48  5383.8 2058.70  5394.2 2060.67
  5404.5 2066.17  5439.1 2071.87  5487.5 2077.29  5521.8 2079.34  5570.4 2080.03
#Mann=4,-1,0
  4597.2    0.07       0  4980.1    0.05       0  5014.7    0.07       0
  5521.8    0.07       0
Bank Sta=4980.1,5014.7
Exp/Cntr=0.3,0.1

Type RM Length L Ch R = 1,9793,319,319,319
BEGIN DESCRIPTION:
North Fork Guadalupe River 18.0
END DESCRIPTION:
XS GIS Cut Line= 3
      1788025.00     13938974.98      1787996.53     13938421.70
      1787725.02     13938025.03
#Sta/Elev= 30
  4449.2 2099.16  4499.2 2094.73  4619.4 2078.95  4679.5 2073.97  4699.5 2065.91
  4729.5 2059.15  4806.2 2054.83  4824.2 2054.33  4869.7 2052.97  4879.7 2050.75
  4969.9 2051.72  4989.9 2050.93  4990.0 2049.48  4991.0 2048.98  5030.0 2049.48
  5032.0 2051.24  5087.8 2052.51  5102.8 2056.68  5108.8 2055.19  5117.7 2058.25
  5123.7 2057.89  5138.6 2065.67  5144.7 2064.47  5153.6 2068.75  5159.6 2066.43
  5168.5 2070.40  5174.5 2069.51  5204.3 2074.32  5347.9 2079.55  5483.9 2079.09
#Mann=6,-1,0
  4449.2    0.07       0  4806.2     0.1       0  4824.2    0.07       0
  4990.0    0.05       0  5030.0    0.07       0  5032.0     0.1       0
Bank Sta=4990,5030
Exp/Cntr=0.3,0.1

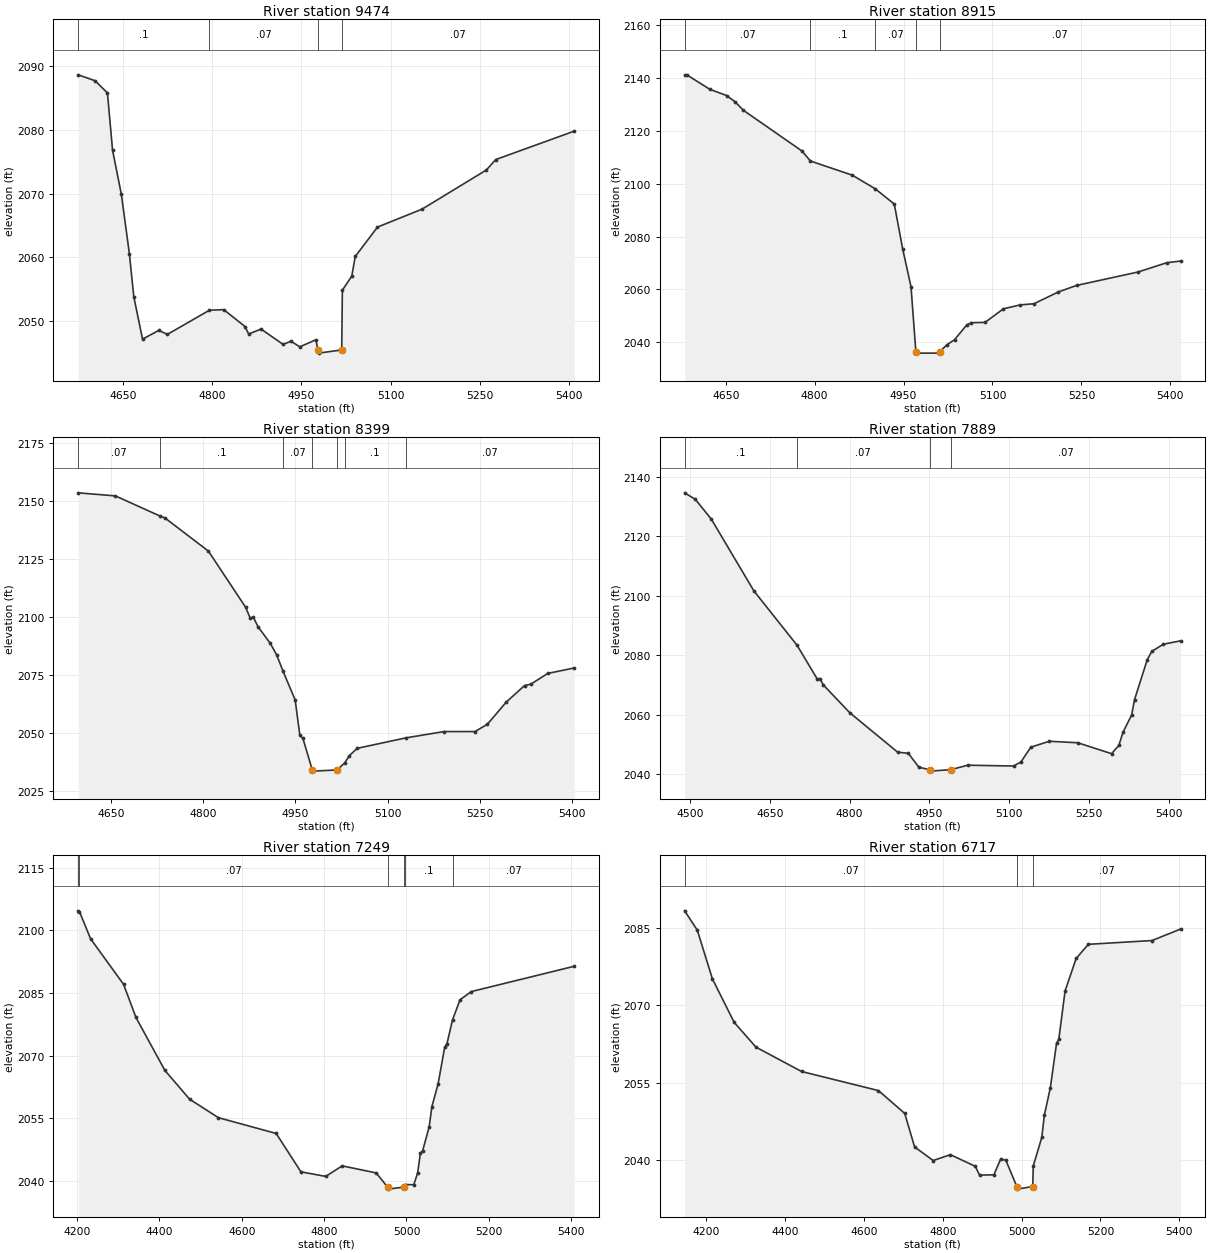
Type RM Length L Ch R = 1,9474,559,559,559
BEGIN DESCRIPTION:
North Fork Guadalupe River 17.0
END DESCRIPTION:
XS GIS Cut Line= 3
      1788624.98     13938574.99      1788275.00     13938325.00
      1787925.01     13938125.00
#Sta/Elev= 30
  4575.2 2088.68  4603.4 2087.76  4624.3 2085.83  4632.9 2076.84  4647.7 2069.89
  4661.2 2060.55  4668.6 2053.80  4683.3 2047.15  4710.4 2048.53  4725.1 2047.91
  4795.7 2051.70  4819.7 2051.79  4855.4 2049.14  4861.5 2047.96  4882.4 2048.74
  4919.3 2046.34  4932.8 2046.82  4947.5 2045.95  4974.6 2047.06  4977.9 2045.46
  4978.9 2044.96  5017.9 2045.46  5019.0 2054.85  5034.8 2057.06  5040.6 2060.14
  5078.0 2064.76  5152.9 2067.58  5260.8 2073.72  5276.7 2075.37  5408.4 2079.83
#Mann=4,-1,0
  4575.2     0.1       0  4795.7    0.07       0  4977.9    0.05       0
  5017.9    0.07       0
Bank Sta=4977.9,5017.9
Exp/Cntr=0.3,0.1

Type RM Length L Ch R = 1,8915,516,516,516
BEGIN DESCRIPTION:
North Fork Guadalupe River 16.0
END DESCRIPTION:
XS GIS Cut Line= 3
      1788875.01     13937674.99      1788575.00     13937975.00
      1788174.98     13938075.00
#Sta/Elev= 30
  4580.8 2141.27  4584.3 2141.27  4623.2 2135.79  4651.5 2133.43  4665.7 2131.08
  4679.8 2127.84  4778.8 2112.39  4792.9 2108.62  4863.6 2103.25  4901.9 2098.15
  4934.4 2092.31  4948.5 2075.36  4962.6 2060.97  4970.8 2036.34  4971.8 2035.84
  5010.0 2035.84  5011.0 2036.34  5023.1 2038.99  5036.0 2040.92  5056.6 2046.49
  5064.3 2047.37  5087.5 2047.49  5118.5 2052.63  5146.8 2054.11  5170.0 2054.55
  5211.2 2059.02  5242.1 2061.50  5345.2 2066.55  5394.2 2070.10  5417.4 2070.73
#Mann=5,-1,0
  4580.8    0.07       0  4792.9     0.1       0  4901.9    0.07       0
  4970.8    0.05       0  5011.0    0.07       0
Bank Sta=4970.8,5011
Exp/Cntr=0.3,0.1

Type RM Length L Ch R = 1,8399,510,510,510
BEGIN DESCRIPTION:
North Fork Guadalupe River 15.0
END DESCRIPTION:
XS GIS Cut Line= 3
      1788774.98     13937475.00      1788375.00     13937525.00
      1787975.01     13937575.00
#Sta/Elev= 30
  4596.9 2153.71  4657.4 2152.38  4730.5 2143.62  4738.0 2142.85  4808.5 2128.59
  4869.0 2104.37  4876.5 2099.67  4881.6 2100.08  4889.1 2095.99  4909.3 2088.72
  4919.4 2083.86  4930.0 2076.69  4949.6 2064.34  4957.2 2049.12  4962.2 2047.78
  4977.4 2034.17  4978.4 2033.67  5017.6 2034.17  5029.8 2037.13  5037.8 2040.39
  5050.4 2043.50  5129.5 2048.01  5191.5 2050.73  5241.9 2050.74  5262.0 2053.86
  5292.3 2063.33  5322.5 2070.60  5332.6 2071.17  5360.3 2075.82  5403.1 2078.16
#Mann=7,-1,0
  4596.9    0.07       0  4730.5     0.1       0  4930.0    0.07       0
  4977.4    0.05       0  5017.6    0.07       0  5029.8     0.1       0
  5129.5    0.07       0
Bank Sta=4977.4,5017.6
Exp/Cntr=0.3,0.1

Type RM Length L Ch R = 1,7889,640,640,640
BEGIN DESCRIPTION:
North Fork Guadalupe River 14.0
END DESCRIPTION:
XS GIS Cut Line= 3
      1788624.99     13937125.00      1788114.45     13937114.93
      1787725.00     13937275.00
#Sta/Elev= 30
  4490.3 2134.58  4510.3 2132.38  4540.3 2125.75  4620.3 2101.62  4701.3 2083.38
  4739.6 2071.92  4744.6 2072.17  4750.3 2070.11  4800.3 2060.69  4890.4 2047.41
  4910.4 2047.04  4930.4 2042.33  4950.3 2041.54  4951.3 2041.04  4990.5 2041.54
  5022.0 2043.03  5108.5 2042.76  5122.1 2044.16  5140.6 2049.08  5175.4 2051.08
  5228.8 2050.57  5292.3 2046.90  5306.0 2049.72  5313.9 2054.17  5330.0 2059.92
  5335.5 2065.11  5359.4 2078.54  5367.9 2081.29  5389.6 2083.70  5422.0 2084.84
#Mann=4,-1,0
  4490.3     0.1       0  4701.3    0.07       0  4950.3    0.05       0
  4990.5    0.07       0
Bank Sta=4950.3,4990.5
Exp/Cntr=0.3,0.1

Type RM Length L Ch R = 1,7249,532,532,532
BEGIN DESCRIPTION:
North Fork Guadalupe River 13.0
END DESCRIPTION:
XS GIS Cut Line= 3
      1788474.98     13936625.00      1787675.00     13936675.00
      1787324.96     13936875.02
#Sta/Elev= 30
  4202.6 2104.66  4205.6 2104.49  4232.6 2097.97  4312.8 2087.05  4342.9 2079.12
  4413.0 2066.46  4473.1 2059.55  4543.2 2055.12  4683.5 2051.34  4743.6 2042.15
  4803.8 2041.06  4843.8 2043.58  4926.5 2041.89  4954.0 2038.51  4955.0 2038.01
  4994.2 2038.51  4997.5 2039.10  5017.8 2039.07  5027.2 2041.93  5033.7 2046.57
  5039.4 2047.24  5055.3 2053.00  5061.7 2057.76  5076.8 2063.20  5092.7 2071.93
  5098.4 2072.85  5111.8 2078.53  5130.1 2083.36  5157.5 2085.32  5407.3 2091.38
#Mann=6,-1,0
  4202.6     0.1       0  4205.6    0.07       0  4954.0    0.05       0
  4994.2    0.07       0  4997.5     0.1       0  5111.8    0.07       0
Bank Sta=4954,4994.2
Exp/Cntr=0.3,0.1

Type RM Length L Ch R = 1,6717,547,547,547
BEGIN DESCRIPTION:
North Fork Guadalupe River 12.0
END DESCRIPTION:
XS GIS Cut Line= 3
      1788374.99     13936475.00      1787575.00     13936175.00
      1787225.00     13936375.00
#Sta/Elev= 30
  4145.7 2088.29  4177.7 2084.54  4216.0 2075.10  4271.2 2066.67  4326.4 2061.87
  4442.1 2057.15  4637.0 2053.45  4703.7 2049.02  4728.6 2042.54  4775.8 2039.89
  4819.4 2041.03  4882.6 2038.77  4893.3 2037.07  4929.8 2037.12  4946.7 2040.16
  4960.0 2039.96  4987.9 2034.85  4988.9 2034.35  5028.2 2034.85  5029.6 2038.85
  5051.2 2044.38  5057.7 2048.68  5072.8 2053.96  5088.6 2062.61  5094.4 2063.43
  5110.2 2072.74  5138.3 2079.06  5169.3 2081.80  5330.5 2082.53  5403.2 2084.76
#Mann=3,-1,0
  4145.7    0.07       0  4987.9    0.05       0  5028.2    0.07       0
Bank Sta=4987.9,5028.2
Exp/Cntr=0.3,0.1