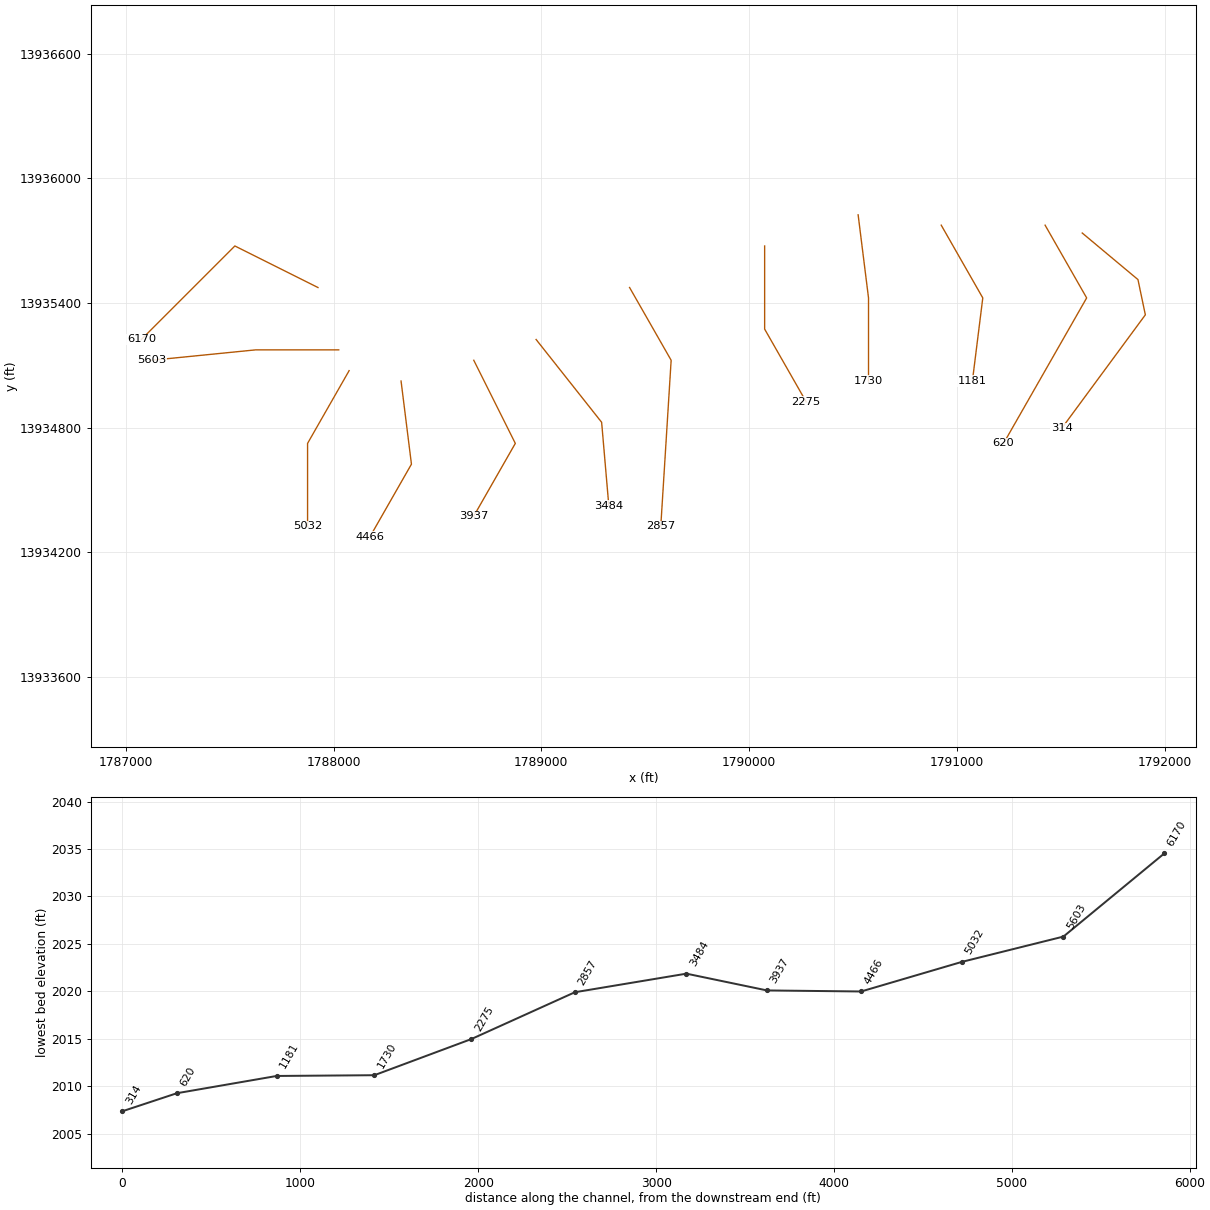
HEC-RAS study North Fork Guadalupe River.prj: North Fork Guadalupe River Base Level Engineering

--- North Fork Guadalupe River.g01 (geometry) --- (continued)

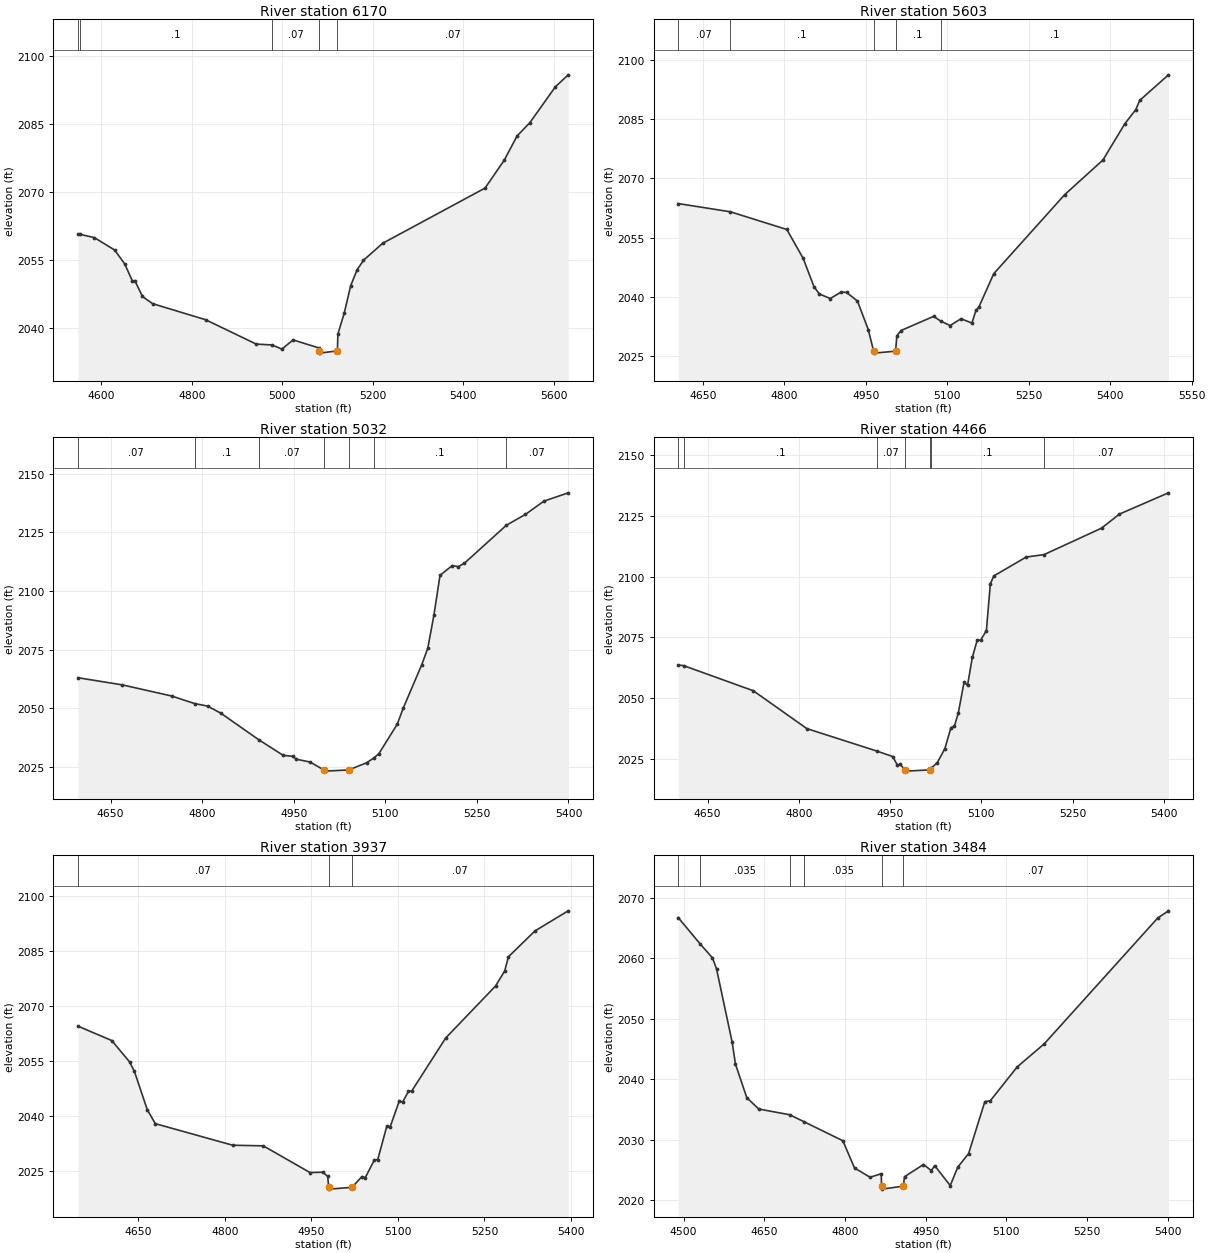
Type RM Length L Ch R = 1,6170,567,567,567
BEGIN DESCRIPTION:
North Fork Guadalupe River 11.0
END DESCRIPTION:
XS GIS Cut Line= 3
      1787925.02     13935474.99      1787525.00     13935675.00
      1787075.02     13935225.02
#Sta/Elev= 30
  4548.4 2060.77  4552.3 2060.73  4584.8 2059.97  4629.5 2057.25  4651.8 2054.19
  4668.6 2050.47  4674.2 2050.50  4691.0 2047.02  4713.3 2045.44  4830.7 2041.89
  4942.5 2036.53  4977.4 2036.34  4999.2 2035.43  5023.9 2037.45  5080.5 2035.70
  5081.5 2035.04  5082.5 2034.54  5121.9 2035.04  5122.9 2038.73  5137.1 2043.40
  5151.2 2049.39  5165.3 2052.86  5179.5 2054.99  5221.9 2058.73  5448.2 2070.89
  5490.6 2077.03  5518.9 2082.35  5547.2 2085.29  5603.7 2093.20  5632.0 2095.83
#Mann=5,-1,0
  4548.4    0.07       0  4552.3     0.1       0  4977.4    0.07       0
  5081.5    0.05       0  5121.9    0.07       0
Bank Sta=5081.5,5121.9
Exp/Cntr=0.3,0.1

Type RM Length L Ch R = 1,5603,571,571,571
BEGIN DESCRIPTION:
North Fork Guadalupe River 10.0
END DESCRIPTION:
XS GIS Cut Line= 3
      1788024.99     13935175.00      1787625.00     13935175.00
      1787124.98     13935125.00
#Sta/Elev= 30
  4604.8 2063.62  4700.9 2061.54  4804.8 2057.06  4834.8 2049.78  4854.8 2042.58
  4864.8 2040.73  4884.8 2039.59  4904.8 2041.23  4914.8 2041.13  4934.8 2038.95
  4954.8 2031.69  4964.6 2026.27  4965.6 2025.77  5005.0 2026.27  5007.3 2030.10
  5014.8 2031.48  5075.1 2035.08  5087.7 2033.91  5105.3 2032.75  5125.4 2034.47
  5145.5 2033.39  5153.0 2036.63  5158.0 2037.34  5185.7 2045.88  5316.3 2065.88
  5386.7 2074.65  5426.9 2083.80  5447.0 2087.37  5454.5 2089.74  5507.3 2096.20
#Mann=5,-1,0
  4604.8    0.07       0  4700.9     0.1       0  4964.6    0.05       0
  5005.0     0.1       0  5087.7     0.1       0
Bank Sta=4964.6,5005
Exp/Cntr=0.3,0.1

Type RM Length L Ch R = 1,5032,566,566,566
BEGIN DESCRIPTION:
North Fork Guadalupe River 9.0
END DESCRIPTION:
XS GIS Cut Line= 3
      1788075.00     13935074.99      1787875.00     13934725.00
      1787875.00     13934325.00
#Sta/Elev= 30
  4596.5 2062.96  4669.2 2059.91  4749.8 2055.17  4787.5 2051.95  4808.8 2050.86
  4830.4 2047.85  4893.1 2036.43  4932.7 2029.84  4948.5 2029.40  4954.3 2028.18
  4976.6 2026.99  4999.4 2023.60  5000.4 2023.10  5039.9 2023.60  5069.6 2026.69
  5081.3 2028.73  5089.6 2030.60  5119.6 2043.15  5129.6 2050.16  5159.6 2068.44
  5169.6 2075.58  5179.6 2089.66  5189.6 2106.65  5209.6 2110.82  5219.6 2110.38
  5229.6 2111.83  5298.2 2128.02  5329.6 2132.67  5359.6 2138.30  5399.6 2141.87
#Mann=7,-1,0
  4596.5    0.07       0  4787.5     0.1       0  4893.1    0.07       0
  4999.4    0.05       0  5039.9    0.07       0  5081.3     0.1       0
  5298.2    0.07       0
Bank Sta=4999.4,5039.9
Exp/Cntr=0.3,0.1

Type RM Length L Ch R = 1,4466,529,529,529
BEGIN DESCRIPTION:
North Fork Guadalupe River 8.0
END DESCRIPTION:
XS GIS Cut Line= 3
      1788325.00     13935025.00      1788375.00     13934625.00
      1788175.01     13934275.03
#Sta/Elev= 30
  4601.5 2063.66  4610.5 2063.40  4725.0 2053.07  4813.1 2037.48  4928.5 2028.21
  4954.2 2025.99  4961.8 2022.53  4966.8 2022.75  4974.3 2020.48  4975.3 2019.98
  5014.8 2020.48  5017.7 2021.17  5027.7 2023.53  5039.9 2029.16  5050.0 2037.87
  5055.7 2038.44  5062.2 2044.05  5071.6 2056.57  5077.3 2055.30  5085.2 2066.79
  5093.2 2073.90  5098.9 2073.89  5108.3 2077.86  5114.8 2097.02  5120.5 2100.32
  5173.8 2108.10  5203.0 2109.09  5297.6 2119.98  5327.1 2125.78  5407.7 2134.53
#Mann=7,-1,0
  4601.5    0.07       0  4610.5     0.1       0  4928.5    0.07       0
  4974.3    0.05       0  5014.8    0.07       0  5017.7     0.1       0
  5203.0    0.07       0
Bank Sta=4974.3,5014.8
Exp/Cntr=0.3,0.1

Type RM Length L Ch R = 1,3937,453,453,453
BEGIN DESCRIPTION:
North Fork Guadalupe River 7.0
END DESCRIPTION:
XS GIS Cut Line= 3
      1788674.98     13935125.04      1788875.00     13934725.00
      1788674.98     13934374.97
#Sta/Elev= 30
  4545.0 2064.53  4603.7 2060.60  4634.5 2054.79  4642.9 2052.22  4665.2 2041.77
  4679.2 2037.94  4813.4 2032.06  4866.5 2031.89  4947.5 2024.61  4969.9 2024.69
  4978.3 2023.56  4979.9 2020.59  4980.9 2020.09  5020.4 2020.59  5037.6 2023.52
  5043.4 2023.22  5059.2 2028.05  5065.0 2028.14  5080.8 2037.28  5086.6 2037.10
  5102.4 2044.12  5108.1 2043.82  5118.2 2046.71  5124.0 2046.85  5183.0 2061.32
  5269.4 2075.48  5285.2 2079.57  5291.7 2083.44  5337.8 2090.50  5395.4 2095.97
#Mann=3,-1,0
  4545.0    0.07       0  4979.9    0.05       0  5020.4    0.07       0
Bank Sta=4979.9,5020.4
Exp/Cntr=0.3,0.1

Type RM Length L Ch R = 1,3484,627,627,627
BEGIN DESCRIPTION:
North Fork Guadalupe River 6.0
END DESCRIPTION:
XS GIS Cut Line= 3
      1788975.02     13935224.97      1789290.42     13934826.47
      1789325.00     13934424.97
#Sta/Elev= 30
  4490.1 2066.76  4531.1 2062.38  4553.8 2060.10  4561.4 2058.26  4590.3 2046.20
  4596.6 2042.52  4617.6 2036.98  4639.9 2035.10  4697.2 2034.16  4724.5 2032.98
  4796.1 2029.86  4817.8 2025.36  4846.7 2023.82  4867.5 2024.41  4868.1 2022.36
  4869.1 2021.86  4908.6 2022.36  4910.8 2023.92  4946.0 2025.93  4960.5 2024.93
  4966.9 2025.74  4995.7 2022.45  5009.8 2025.50  5029.9 2027.75  5060.0 2036.32
  5070.1 2036.46  5120.2 2042.07  5170.4 2045.88  5381.2 2066.67  5401.3 2067.87
#Mann=6,-1,0
  4490.1    0.07       0  4531.1   0.035       0  4697.2    0.07       0
  4724.5   0.035       0  4868.1    0.05       0  4908.6    0.07       0
Bank Sta=4868.1,4908.6
Exp/Cntr=0.3,0.1

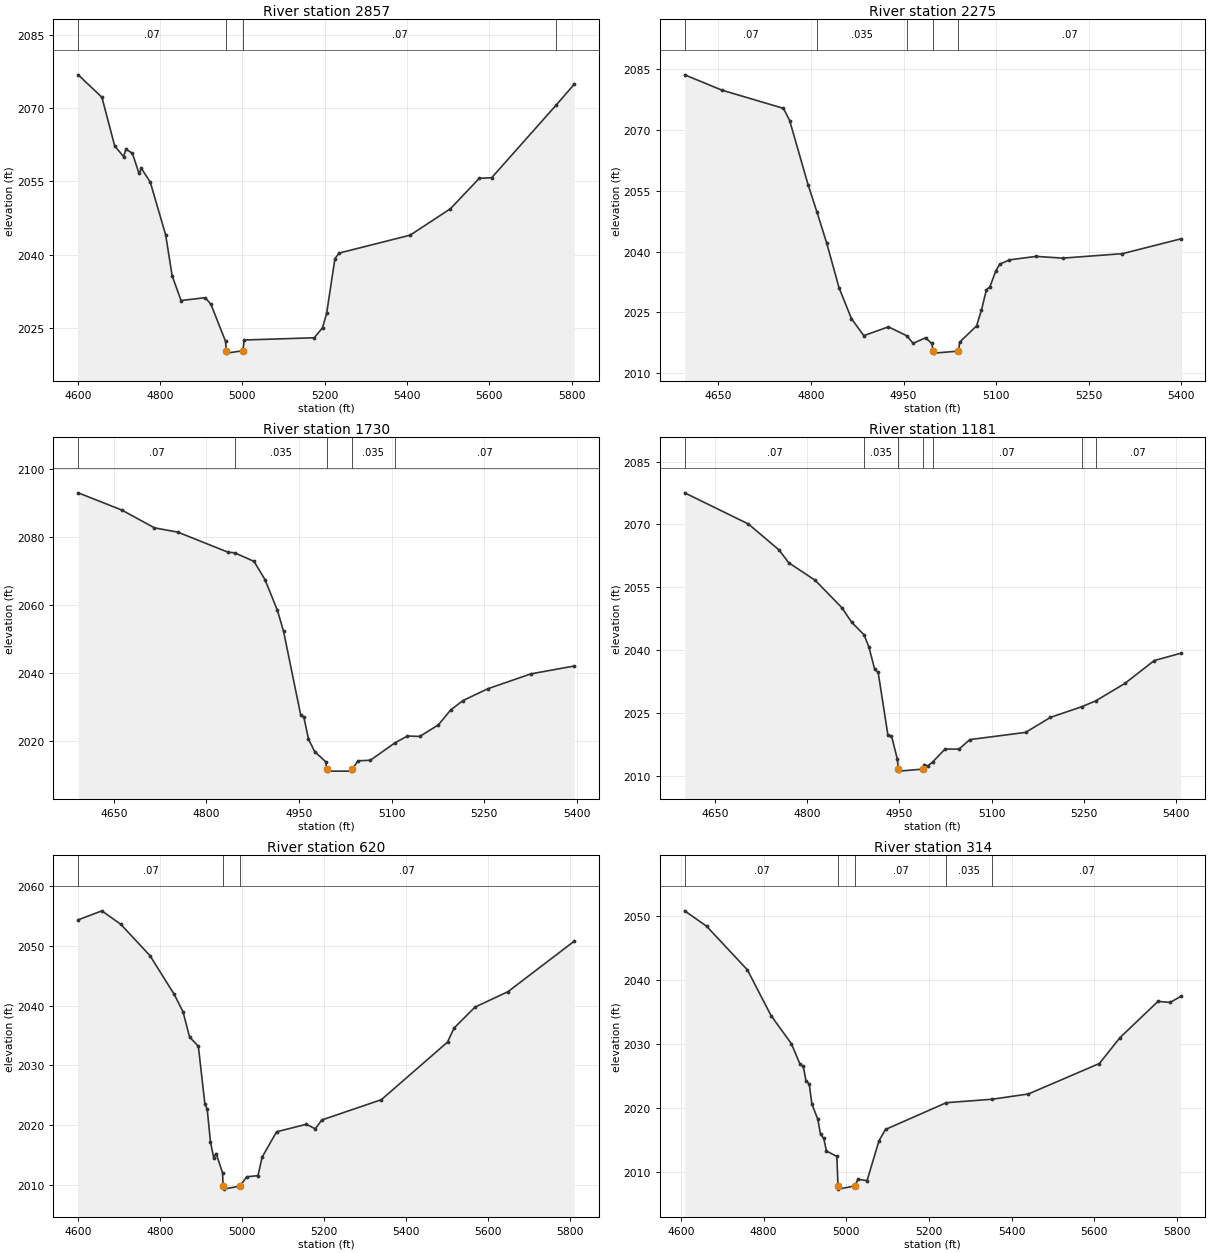
Type RM Length L Ch R = 1,2857,582,582,582
BEGIN DESCRIPTION:
North Fork Guadalupe River 5.0
END DESCRIPTION:
XS GIS Cut Line= 3
      1789424.98     13935475.03      1789625.00     13935125.00
      1789575.00     13934325.01
#Sta/Elev= 30
  4601.2 2076.77  4658.8 2072.18  4689.8 2062.25  4711.4 2060.06  4717.1 2061.58
  4733.0 2060.72  4748.8 2056.62  4754.6 2057.65  4776.2 2054.85  4813.6 2044.07
  4829.4 2035.71  4851.0 2030.65  4910.0 2031.23  4923.7 2029.85  4959.0 2022.33
  4961.0 2020.40  4962.0 2019.90  5001.6 2020.40  5004.3 2022.58  5174.7 2023.04
  5194.7 2025.09  5204.7 2028.05  5224.8 2039.21  5234.8 2040.34  5407.6 2044.01
  5505.3 2049.40  5575.5 2055.63  5605.5 2055.74  5762.1 2070.58  5805.9 2074.83
#Mann=4,-1,0
  4601.2    0.07       0  4961.0    0.05       0  5001.6    0.07       0
  5762.1     0.1       0
Bank Sta=4961,5001.6
Exp/Cntr=0.3,0.1

Type RM Length L Ch R = 1,2275,545,545,545
BEGIN DESCRIPTION:
North Fork Guadalupe River 4.0
END DESCRIPTION:
XS GIS Cut Line= 3
      1790075.00     13935674.96      1790075.00     13935275.00
      1790275.01     13934924.98
#Sta/Elev= 30
  4595.6 2083.57  4655.6 2079.81  4755.6 2075.30  4765.6 2072.29  4795.6 2056.40
  4809.8 2049.75  4825.6 2042.08  4845.6 2031.06  4865.6 2023.48  4885.6 2019.27
  4925.6 2021.44  4955.0 2019.25  4965.6 2017.38  4985.6 2018.74  4995.6 2017.37
  4998.3 2015.46  4999.3 2014.96  5038.9 2015.46  5040.9 2017.67  5068.3 2021.68
  5076.2 2025.56  5084.1 2030.54  5089.9 2031.32  5099.2 2035.14  5105.7 2036.88
  5121.5 2037.95  5164.7 2038.81  5207.9 2038.38  5304.4 2039.48  5398.7 2043.12
#Mann=5,-1,0
  4595.6    0.07       0  4809.8   0.035       0  4955.0    0.07       0
  4998.3    0.05       0  5038.9    0.07       0
Bank Sta=4998.3,5038.9
Exp/Cntr=0.3,0.1

Type RM Length L Ch R = 1,1730,549,549,549
BEGIN DESCRIPTION:
North Fork Guadalupe River 3.0
END DESCRIPTION:
XS GIS Cut Line= 3
      1790525.00     13935825.02      1790575.00     13935425.00
      1790575.00     13935025.03
#Sta/Elev= 30
  4592.3 2092.92  4662.9 2087.86  4715.8 2082.63  4753.6 2081.37  4834.2 2075.53
  4846.0 2075.27  4877.0 2072.78  4894.7 2067.43  4914.8 2058.44  4924.9 2052.19
  4952.6 2027.63  4957.6 2027.12  4965.2 2020.55  4975.3 2016.87  4992.9 2013.93
  4995.1 2011.65  4996.1 2011.15  5034.7 2011.15  5035.7 2011.65  5045.4 2014.18
  5065.4 2014.35  5105.0 2019.43  5125.4 2021.47  5145.4 2021.34  5175.4 2024.72
  5195.4 2029.11  5215.4 2031.89  5255.4 2035.34  5325.4 2039.73  5395.4 2042.03
#Mann=5,-1,0
  4592.3    0.07       0  4846.0   0.035       0  4995.1   0.035       0
  5035.7   0.035       0  5105.0    0.07       0
Bank Sta=4995.1,5035.7
Exp/Cntr=0.3,0.1

Type RM Length L Ch R = 1,1181,561,561,561
BEGIN DESCRIPTION:
North Fork Guadalupe River 2.0
END DESCRIPTION:
XS GIS Cut Line= 3
      1790924.98     13935775.04      1791125.00     13935425.00
      1791075.00     13935024.97
#Sta/Elev= 30
  4601.0 2077.52  4704.7 2070.07  4754.4 2063.88  4770.2 2060.83  4813.4 2056.61
  4856.6 2050.09  4872.4 2046.63  4892.8 2043.59  4900.5 2040.70  4909.9 2035.41
  4915.6 2034.64  4931.5 2019.60  4937.2 2019.50  4946.6 2014.04  4948.5 2011.57
  4949.5 2011.07  4989.2 2011.57  4990.5 2012.65  4996.2 2012.29  5004.0 2013.23
  5024.3 2016.34  5047.0 2016.33  5064.6 2018.60  5155.3 2020.32  5195.6 2023.90
  5246.4 2026.44  5269.2 2027.84  5316.6 2032.00  5364.4 2037.47  5407.3 2039.21
#Mann=7,-1,0
  4601.0    0.07       0  4892.8   0.035       0  4948.5   0.035       0
  4989.2   0.035       0  5004.0    0.07       0  5246.4     0.1       0
  5269.2    0.07       0
Bank Sta=4948.5,4989.2
Exp/Cntr=0.3,0.1

Type RM Length L Ch R = 1,620,306,306,306
BEGIN DESCRIPTION:
North Fork Guadalupe River 1.0
END DESCRIPTION:
XS GIS Cut Line= 3
      1791424.98     13935775.03      1791625.00     13935425.00
      1791224.99     13934724.97
#Sta/Elev= 30
  4600.7 2054.40  4658.3 2055.91  4704.4 2053.66  4775.7 2048.40  4834.7 2041.92
  4856.3 2038.99  4872.1 2034.79  4893.7 2033.19  4909.5 2023.60  4915.3 2022.62
  4923.2 2017.16  4931.1 2014.52  4936.9 2015.22  4952.7 2011.99  4954.0 2009.75
  4955.0 2009.25  4994.7 2009.75  5011.8 2011.32  5039.1 2011.51  5049.2 2014.62
  5084.5 2018.87  5157.2 2020.12  5178.8 2019.36  5194.6 2020.84  5340.0 2024.25
  5501.3 2033.90  5517.1 2036.25  5568.2 2039.76  5648.8 2042.36  5810.1 2050.81
#Mann=3,-1,0
  4600.7    0.07       0  4954.0    0.05       0  4994.7    0.07       0
Bank Sta=4954,4994.7
Exp/Cntr=0.3,0.1

Type RM Length L Ch R = 1,314,0,0,0
BEGIN DESCRIPTION:
North Fork Guadalupe River 0.0
END DESCRIPTION:
XS GIS Cut Line= 4
      1791603.66     13935737.29      1791871.89     13935513.29
      1791907.46     13935343.55      1791505.74     13934798.49
#Sta/Elev= 30
  4608.9 2050.75  4661.7 2048.36  4760.6 2041.55  4817.8 2034.42  4867.3 2030.01
  4888.1 2026.82  4895.9 2026.49  4902.4 2024.23  4910.2 2023.77  4916.8 2020.59
  4931.1 2018.25  4937.6 2015.88  4945.4 2015.26  4951.9 2013.30  4977.1 2012.45
  4979.9 2007.85  4980.9 2007.35  5020.6 2007.85  5028.1 2008.88  5050.2 2008.68
  5079.2 2014.92  5095.0 2016.66  5242.0 2020.83  5353.1 2021.37  5440.6 2022.19
  5612.3 2026.94  5662.4 2030.99  5754.2 2036.63  5783.5 2036.47  5808.9 2037.39
#Mann=5,-1,0
  4608.9    0.07       0  4979.9    0.05       0  5020.6    0.07       0
  5242.0   0.035       0  5353.1    0.07       0
Bank Sta=4979.9,5020.6
Exp/Cntr=0.3,0.1

Chan Stop Cuts=-1