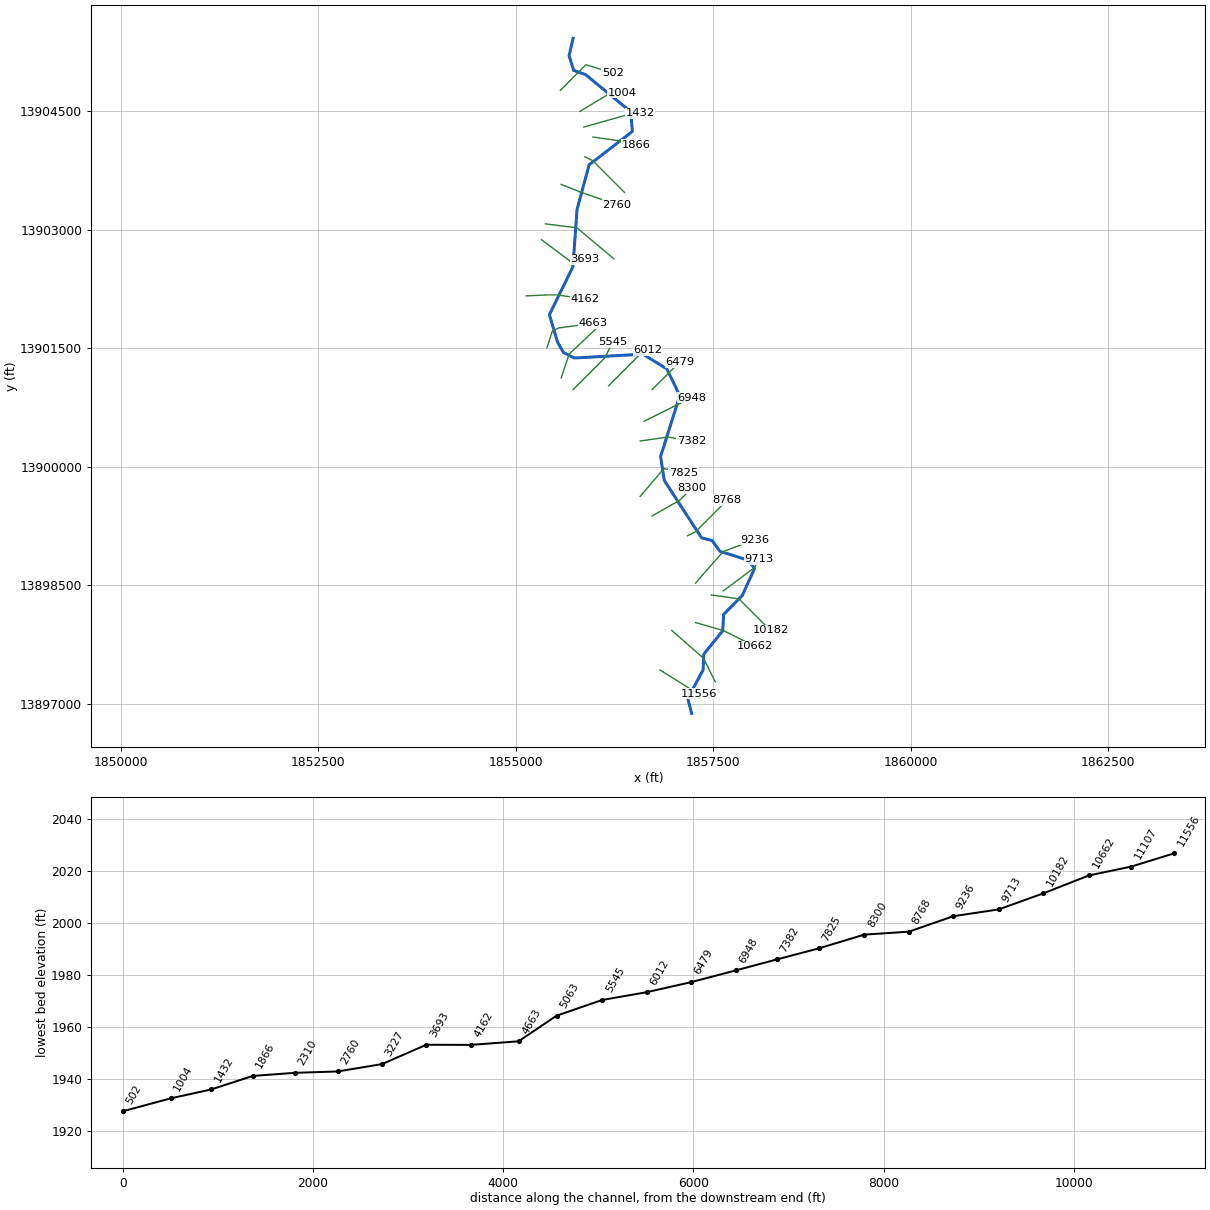
--- Pecan Creek.prj (project) ---

Proj Title=Pecan Creek Base Level Engineering
Current Plan=p01
Default Exp/Contr=0.3,0.1
English Units
Geom File=g01
Flow File=f01
Plan File=p01
BEGIN DESCRIPTION:
Pecan Creek
END DESCRIPTION:

--- Pecan Creek.p01 (plan) ---

Plan Title=Multiple Run
Short Identifier=Multiple
Geom File=g01
Flow File=f01
Subcritical Flow
K Sum by GR= 0
Std Step Tol= 0.01
Critical Tol= 0.01
Num of Std Step Trials= 20
Max Error Tol= 0.3
Flow Tol Ratio= 0.001
Split Flow NTrial= 30
Split Flow Tol= 0.02
Split Flow Ratio= 0.02
Log Output Level= 0
Friction Slope Method= 1
Unsteady Friction Slope Method= 2
Unsteady Bridges Friction Slope Method= 1
Parabolic Critical Depth
Global Vel Dist=  1 , 1 , 1
Global Log Level= 0
CheckData=True
Encroach Param= -1, 0, 0, 0
BEGIN DESCRIPTION:
Multiple Run
END DESCRIPTION:

--- Pecan Creek.f01 (steady flow) ---

Flow Title=Multiple
Number of Profiles=7
Profile Names=10-year,25-year,50-year,1pct_min,100-year,1pct_plu,500-year
River Rch & RM= Pecan Creek,Reach-1,11556
    2320    4130    5922    4096    8172   16305   15392
River Rch & RM= Pecan Creek,Reach-1,4162
    2893    5193    7488    5201   10377   20705   19725
Boundary for River Rch & Prof#=Pecan Creek,Reach-1,1
Up Type=0
Dn Type=3
Dn Slope=0.005
Boundary for River Rch & Prof#=Pecan Creek,Reach-1,2
Up Type=0
Dn Type=3
Dn Slope=0.005
Boundary for River Rch & Prof#=Pecan Creek,Reach-1,3
Up Type=0
Dn Type=3
Dn Slope=0.005
Boundary for River Rch & Prof#=Pecan Creek,Reach-1,4
Up Type=0
Dn Type=3
Dn Slope=0.005
Boundary for River Rch & Prof#=Pecan Creek,Reach-1,5
Up Type=0
Dn Type=3
Dn Slope=0.005
Boundary for River Rch & Prof#=Pecan Creek,Reach-1,6
Up Type=0
Dn Type=3
Dn Slope=0.005
Boundary for River Rch & Prof#=Pecan Creek,Reach-1,7
Up Type=0
Dn Type=3
Dn Slope=0.005

--- Pecan Creek.g01 (geometry) ---

Geom Title=Existing Conditions

River Reach=Pecan Creek,Reach-1
Reach XY= 30
      1857225.00     13896875.00      1857176.18     13897064.50
      1857371.25     13897426.55      1857378.55     13897623.53
      1857619.54     13897922.55      1857630.46     13898127.45
      1857866.84     13898368.95      1858024.07     13898714.53
      1857927.44     13898819.48      1857583.31     13898928.08
      1857484.81     13899064.49      1857351.42     13899097.85
      1856878.75     13899826.55      1856833.08     13900128.30
      1857075.41     13900900.00      1856911.61     13901238.33
      1856609.79     13901424.49      1855740.96     13901375.95
      1855604.48     13901444.47      1855528.82     13901576.58
      1855425.00     13901925.00      1855722.82     13902530.45
      1855775.68     13903261.08      1855928.61     13903823.50
      1856475.09     13904244.88      1856455.41     13904495.20
      1855881.17     13904967.14      1855732.73     13905018.50
      1855674.64     13905204.85      1855725.00     13905425.00

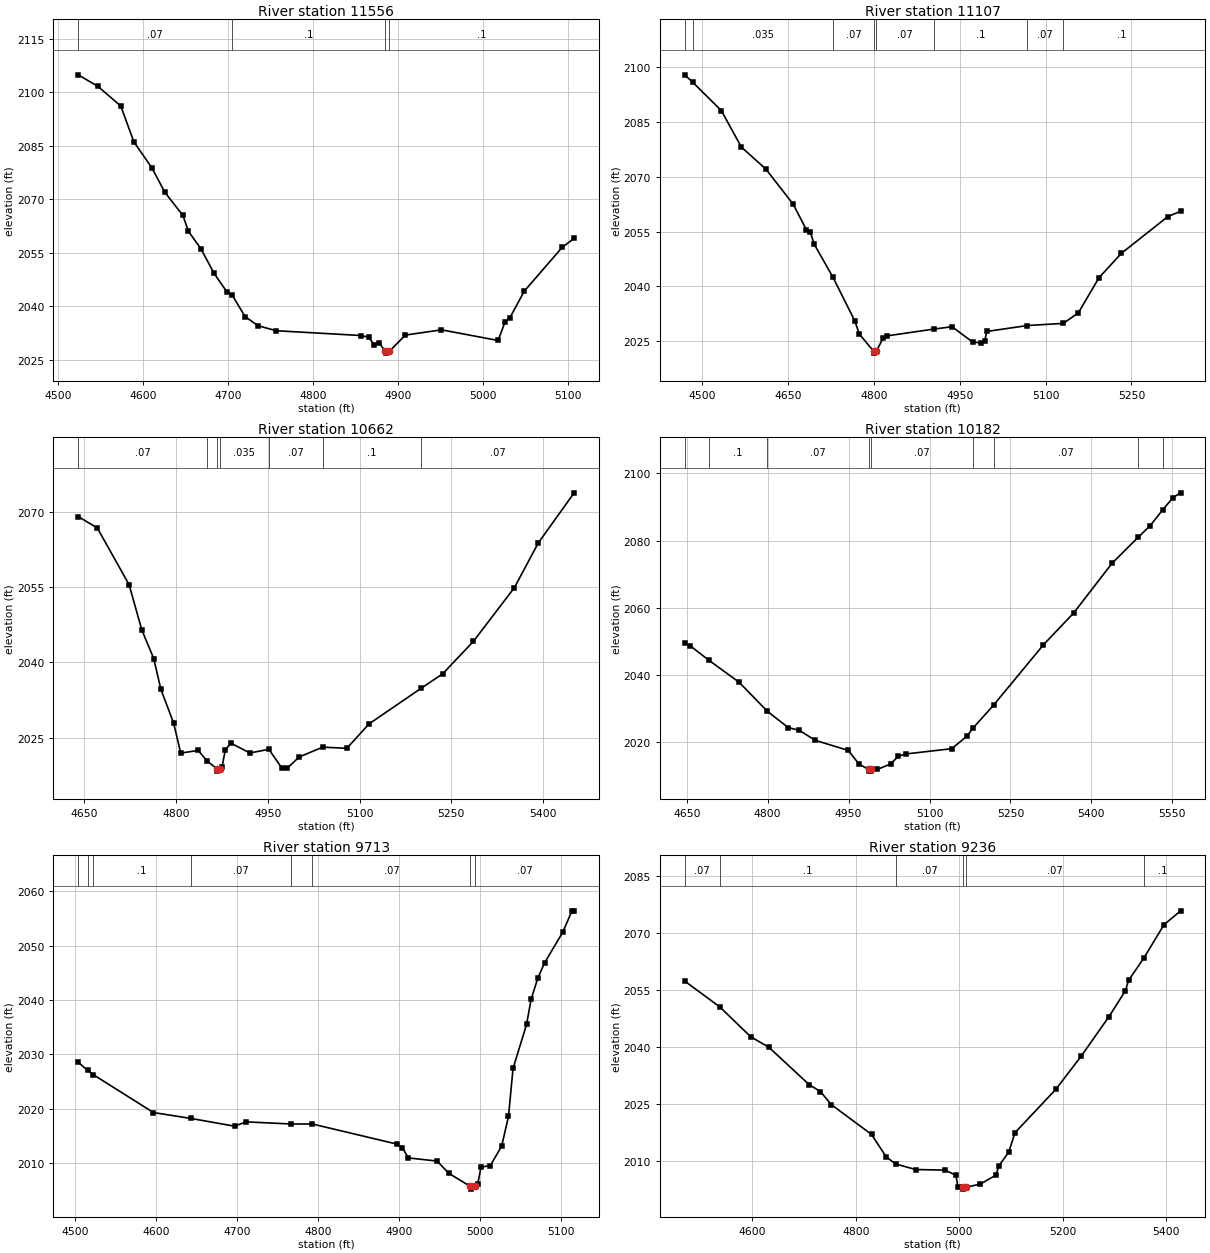
Type RM Length L Ch R = 1,11556,449,449,449
BEGIN DESCRIPTION:
Pecan Creek 24.0
END DESCRIPTION:
XS GIS Cut Line= 3
      1856825.03     13897424.98      1857225.00     13897175.00
      1857325.03     13897124.99
#Sta/Elev= 30
  4523.8 2104.94  4546.8 2101.73  4573.9 2096.18  4589.2 2086.17  4610.4 2078.84
  4625.8 2071.93  4647.0 2065.45  4653.5 2060.99  4668.2 2056.09  4683.6 2049.22
  4698.9 2043.93  4705.1 2043.04  4720.1 2037.06  4735.4 2034.50  4756.7 2033.09
  4856.9 2031.74  4865.7 2031.23  4872.2 2029.04  4878.1 2029.58  4885.3 2027.30
  4885.6 2026.80  4889.9 2027.30  4908.8 2031.87  4951.2 2033.34  5017.8 2030.35
  5026.2 2035.67  5031.8 2036.77  5048.6 2044.20  5093.3 2056.52  5107.3 2059.02
#Mann=4,-1,0
  4523.8    0.07       0  4705.1     0.1       0  4885.3    0.05       0
  4889.9     0.1       0
Bank Sta=4885.3,4889.9
Exp/Cntr=0.3,0.1

Type RM Length L Ch R = 1,11107,445,445,445
BEGIN DESCRIPTION:
Pecan Creek 23.0
END DESCRIPTION:
XS GIS Cut Line= 3
      1856975.03     13897924.98      1857375.00     13897575.00
      1857525.01     13897274.99
#Sta/Elev= 30
  4469.1 2097.87  4483.5 2095.79  4533.1 2088.10  4568.2 2078.10  4611.0 2072.09
  4658.9 2062.44  4681.7 2055.53  4688.8 2054.85  4695.4 2051.55  4728.4 2042.46
  4766.6 2030.50  4774.2 2027.00  4799.4 2022.23  4799.7 2021.73  4804.0 2022.23
  4816.0 2025.84  4823.6 2026.47  4904.7 2028.31  4936.5 2028.95  4972.6 2024.74
  4986.8 2024.56  4993.5 2025.06  4997.3 2027.66  5068.1 2029.28  5130.7 2029.86
  5157.1 2032.72  5193.4 2042.38  5232.6 2049.05  5313.6 2059.08  5336.0 2060.55
#Mann=8,-1,0
  4469.1    0.07       0  4483.5   0.035       0  4728.4    0.07       0
  4799.4    0.05       0  4804.0    0.07       0  4904.7     0.1       0
  5068.1    0.07       0  5130.7     0.1       0
Bank Sta=4799.4,4804
Exp/Cntr=0.3,0.1

Type RM Length L Ch R = 1,10662,480,480,480
BEGIN DESCRIPTION:
Pecan Creek 22.0
END DESCRIPTION:
XS GIS Cut Line= 3
      1857275.02     13898024.99      1857625.00     13897925.00
      1858025.00     13897725.00
#Sta/Elev= 30
  4639.9 2069.08  4671.1 2066.82  4723.1 2055.52  4743.9 2046.49  4763.4 2040.78
  4775.1 2034.65  4795.9 2027.93  4807.6 2021.93  4836.2 2022.45  4850.3 2020.40
  4866.3 2018.83  4866.7 2018.33  4871.0 2018.83  4875.2 2019.17  4880.4 2022.51
  4889.5 2023.91  4920.7 2021.95  4951.8 2022.68  4972.7 2018.99  4981.8 2018.91
  5001.3 2021.15  5039.8 2023.11  5079.3 2022.88  5115.7 2027.76  5201.2 2034.88
  5235.9 2037.72  5286.2 2044.19  5353.3 2054.90  5392.4 2063.82  5451.1 2073.82
#Mann=7,-1,0
  4639.9    0.07       0  4850.3   0.035       0  4866.3    0.05       0
  4871.0   0.035       0  4951.8    0.07       0  5039.8     0.1       0
  5201.2    0.07       0
Bank Sta=4866.3,4871
Exp/Cntr=0.3,0.1

Type RM Length L Ch R = 1,10182,469,469,469
BEGIN DESCRIPTION:
Pecan Creek 21.0
END DESCRIPTION:
XS GIS Cut Line= 3
      1857474.99     13898375.00      1857825.00     13898325.00
      1858224.97     13897925.03
#Sta/Elev= 30
  4646.2 2049.43  4656.3 2048.72  4691.0 2044.41  4747.2 2037.85  4799.7 2029.18
  4838.1 2024.40  4858.3 2023.58  4888.6 2020.57  4949.3 2017.61  4969.5 2013.50
  4987.2 2011.94  4987.6 2011.44  4991.7 2011.44  4992.1 2011.94  5003.3 2011.96
  5028.0 2013.56  5042.2 2015.88  5056.3 2016.55  5141.2 2018.11  5169.5 2021.86
  5180.0 2024.13  5218.9 2031.09  5310.9 2048.96  5367.5 2058.52  5438.2 2073.22
  5486.3 2080.91  5508.9 2084.39  5532.4 2089.16  5551.3 2092.77  5565.4 2094.18
#Mann=9,-1,0
  4646.2    0.07       0  4691.0     0.1       0  4799.7    0.07       0
  4987.2    0.05       0  4992.1    0.07       0  5180.0     0.1       0
  5218.9    0.07       0  5486.3     0.1       0  5532.4    0.07       0
Bank Sta=4987.2,4992.1
Exp/Cntr=0.3,0.1

Type RM Length L Ch R = 1,9713,477,477,477
BEGIN DESCRIPTION:
Pecan Creek 20.0
END DESCRIPTION:
XS GIS Cut Line= 3
      1857624.97     13898424.97      1858025.00     13898725.00
      1858074.98     13898824.96
#Sta/Elev= 30
  4503.9 2028.58  4515.5 2027.07  4522.6 2026.29  4596.7 2019.34  4642.9 2018.26
  4696.7 2016.84  4711.2 2017.63  4766.4 2017.24  4792.7 2017.24  4896.7 2013.56
  4903.9 2012.86  4911.2 2011.01  4946.7 2010.43  4961.2 2008.17  4987.6 2005.78
  4988.1 2005.28  4993.2 2005.78  4996.7 2006.18  5000.8 2009.32  5012.3 2009.60
  5026.3 2013.19  5034.7 2018.63  5040.3 2027.43  5057.0 2035.52  5062.6 2040.12
  5071.0 2044.09  5079.4 2046.87  5101.8 2052.50  5113.0 2056.38  5115.7 2056.38
#Mann=8,-1,0
  4503.9     0.1       0  4515.5    0.07       0  4522.6     0.1       0
  4642.9    0.07       0  4766.4     0.1       0  4792.7    0.07       0
  4987.6    0.05       0  4993.2    0.07       0
Bank Sta=4987.6,4993.2
Exp/Cntr=0.3,0.1

Type RM Length L Ch R = 1,9236,468,468,468
BEGIN DESCRIPTION:
Pecan Creek 19.0
END DESCRIPTION:
XS GIS Cut Line= 3
      1857274.97     13898524.97      1857625.00     13898925.00
      1858025.05     13899075.02
#Sta/Elev= 30
  4469.1 2057.34  4537.1 2050.54  4596.8 2042.70  4631.9 2039.95  4709.7 2030.13
  4731.6 2028.31  4752.5 2024.89  4830.3 2017.05  4858.8 2011.14  4876.9 2009.29
  4915.7 2007.83  4972.7 2007.67  4993.5 2006.30  4997.3 2003.33  5007.6 2003.18
  5008.1 2002.68  5013.3 2003.18  5040.7 2004.01  5071.0 2006.37  5076.3 2008.72
  5095.9 2012.48  5107.5 2017.49  5186.7 2028.90  5235.6 2037.60  5289.0 2047.91
  5321.1 2054.77  5327.3 2057.52  5357.3 2063.50  5395.8 2072.14  5427.9 2075.79
#Mann=6,-1,0
  4469.1    0.07       0  4537.1     0.1       0  4876.9    0.07       0
  5007.6    0.05       0  5013.3    0.07       0  5357.3     0.1       0
Bank Sta=5007.6,5013.3
Exp/Cntr=0.3,0.1

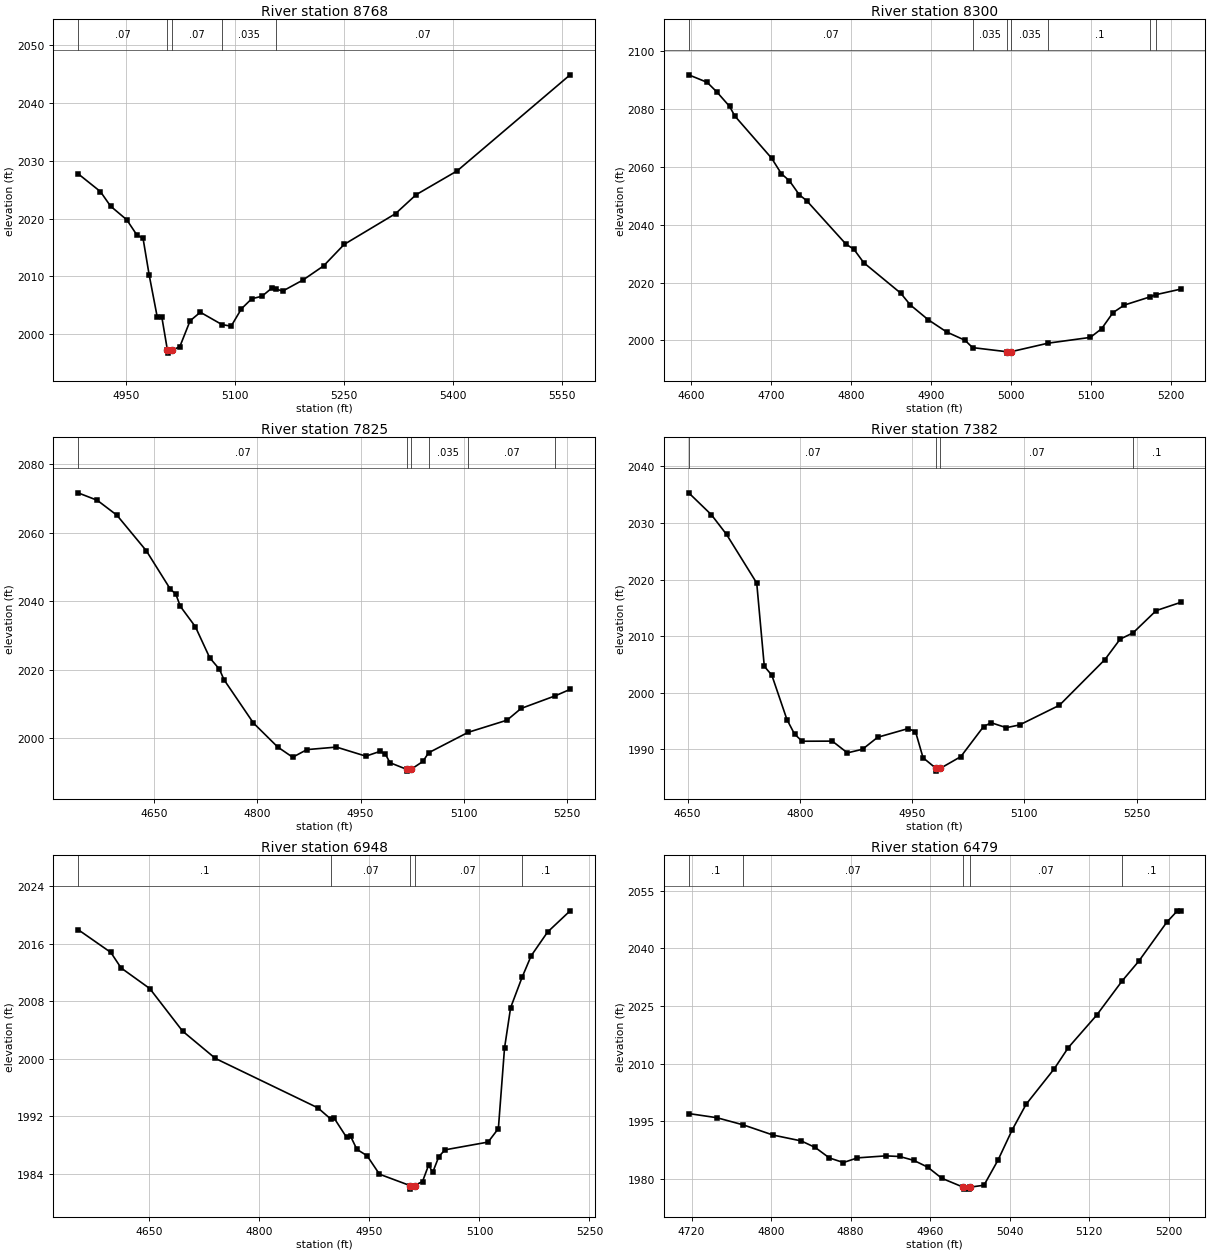
Type RM Length L Ch R = 1,8768,468,468,468
BEGIN DESCRIPTION:
Pecan Creek 18.0
END DESCRIPTION:
XS GIS Cut Line= 3
      1857174.96     13899124.98      1857275.00     13899175.00
      1857674.98     13899574.98
#Sta/Elev= 30
  4883.8 2027.76  4914.6 2024.67  4928.6 2022.15  4950.9 2019.79  4964.9 2017.15
  4973.3 2016.60  4981.7 2010.29  4992.9 2002.95  4999.2 2002.95  5006.9 1997.23
  5007.3 1996.73  5012.7 1997.23  5023.9 1997.83  5038.1 2002.32  5052.2 2003.80
  5081.9 2001.67  5094.6 2001.39  5108.8 2004.40  5122.9 2006.13  5137.1 2006.57
  5151.2 2008.04  5156.6 2007.82  5165.4 2007.45  5193.6 2009.38  5221.9 2011.82
  5250.2 2015.53  5320.9 2020.85  5349.2 2024.12  5405.8 2028.25  5561.3 2044.86
#Mann=5,-1,0
  4883.8    0.07       0  5006.9    0.05       0  5012.7    0.07       0
  5081.9   0.035       0  5156.6    0.07       0
Bank Sta=5006.9,5012.7
Exp/Cntr=0.3,0.1

Type RM Length L Ch R = 1,8300,475,475,475
BEGIN DESCRIPTION:
Pecan Creek 17.0
END DESCRIPTION:
XS GIS Cut Line= 3
      1856725.03     13899375.02      1857075.00     13899575.00
      1857224.99     13899724.99
#Sta/Elev= 30
  4596.7 2091.84  4619.7 2089.25  4631.9 2085.91  4647.8 2080.92  4654.3 2077.61
  4700.3 2063.02  4712.6 2057.62  4722.6 2055.20  4734.9 2050.38  4744.2 2048.30
  4793.2 2033.32  4803.3 2031.48  4815.5 2026.87  4861.6 2016.37  4873.8 2012.25
  4896.1 2007.15  4919.2 2002.91  4942.2 2000.03  4951.5 1997.51  4994.0 1996.10
  4994.4 1995.60  4999.8 1996.10  5046.1 1999.05  5098.8 2001.04  5112.9 2004.04
  5127.1 2009.60  5141.2 2012.21  5174.0 2015.10  5181.2 2015.84  5211.9 2017.74
#Mann=7,-1,0
  4596.7    0.07       0  4951.5   0.035       0  4994.0   0.035       0
  4999.8   0.035       0  5046.1     0.1       0  5174.0    0.07       0
  5181.2     0.1       0
Bank Sta=4994,4999.8
Exp/Cntr=0.3,0.1

Type RM Length L Ch R = 1,7825,443,443,443
BEGIN DESCRIPTION:
Pecan Creek 16.0
END DESCRIPTION:
XS GIS Cut Line= 3
      1856574.97     13899624.96      1856875.00     13899975.00
      1857125.02     13899925.00
#Sta/Elev= 30
  4538.9 2071.63  4566.9 2069.45  4595.5 2065.09  4638.3 2054.70  4673.4 2043.44
  4681.1 2042.10  4687.7 2038.50  4709.6 2032.54  4730.5 2023.47  4744.7 2020.09
  4751.3 2017.05  4794.1 2004.40  4829.3 1997.42  4851.2 1994.41  4872.1 1996.64
  4914.9 1997.37  4957.7 1994.72  4978.5 1996.13  4986.2 1995.28  4992.8 1992.81
  5017.4 1990.85  5017.9 1990.35  5023.3 1990.85  5040.7 1993.18  5049.0 1995.71
  5106.5 2001.68  5163.1 2005.23  5183.5 2008.65  5233.2 2012.34  5254.9 2014.23
#Mann=6,-1,0
  4538.9    0.07       0  5017.4    0.05       0  5023.3    0.07       0
  5049.0   0.035       0  5106.5    0.07       0  5233.2     0.1       0
Bank Sta=5017.4,5023.3
Exp/Cntr=0.3,0.1

Type RM Length L Ch R = 1,7382,434,434,434
BEGIN DESCRIPTION:
Pecan Creek 15.0
END DESCRIPTION:
XS GIS Cut Line= 3
      1856574.99     13900325.00      1856925.00     13900375.00
      1857225.00     13900325.00
#Sta/Elev= 30
  4651.5 2035.34  4681.8 2031.46  4702.0 2027.99  4742.4 2019.37  4752.5 2004.65
  4762.6 2003.06  4782.8 1995.21  4792.9 1992.66  4803.0 1991.38  4843.4 1991.40
  4863.6 1989.32  4883.8 1989.96  4904.0 1992.08  4944.5 1993.61  4954.6 1993.09
  4964.7 1988.46  4981.9 1986.59  4982.4 1986.09  4987.9 1986.59  5015.2 1988.66
  5045.6 1993.98  5055.8 1994.65  5076.0 1993.78  5093.8 1994.27  5147.0 1997.75
  5207.8 2005.84  5228.1 2009.45  5245.3 2010.55  5276.3 2014.50  5309.2 2015.96
#Mann=4,-1,0
  4651.5    0.07       0  4981.9    0.05       0  4987.9    0.07       0
  5245.3     0.1       0
Bank Sta=4981.9,4987.9
Exp/Cntr=0.3,0.1

Type RM Length L Ch R = 1,6948,469,469,469
BEGIN DESCRIPTION:
Pecan Creek 14.0
END DESCRIPTION:
XS GIS Cut Line= 3
      1856625.02     13900575.01      1857025.00     13900775.00
      1857225.00     13900875.00
#Sta/Elev= 30
  4552.8 2017.98  4597.5 2014.80  4611.5 2012.64  4650.6 2009.77  4695.3 2003.85
  4740.1 2000.04  4879.8 1993.16  4897.6 1991.58  4902.2 1991.69  4918.9 1989.05
  4924.5 1989.18  4932.9 1987.39  4946.9 1986.49  4963.7 1983.93  5005.2 1982.35
  5005.7 1981.85  5011.5 1982.35  5022.4 1982.91  5030.7 1985.19  5036.3 1984.19
  5044.7 1986.39  5053.1 1987.32  5111.8 1988.40  5125.8 1990.28  5134.2 2001.50
  5142.5 2007.11  5158.1 2011.33  5170.5 2014.33  5192.9 2017.64  5223.6 2020.59
#Mann=5,-1,0
  4552.8     0.1       0  4897.6    0.07       0  5005.2    0.05       0
  5011.5    0.07       0  5158.1     0.1       0
Bank Sta=5005.2,5011.5
Exp/Cntr=0.3,0.1

Type RM Length L Ch R = 1,6479,467,467,467
BEGIN DESCRIPTION:
Pecan Creek 13.0
END DESCRIPTION:
XS GIS Cut Line= 3
      1856724.98     13900974.98      1856925.00     13901175.00
      1857074.99     13901324.99
#Sta/Elev= 30
  4717.1 1997.01  4745.4 1995.93  4771.9 1994.07  4802.0 1991.41  4830.3 1989.89
  4844.4 1988.18  4858.6 1985.46  4872.7 1984.27  4886.8 1985.48  4915.1 1986.00
  4929.3 1985.84  4943.4 1984.84  4957.5 1983.07  4971.7 1980.17  4993.3 1977.85
  4993.8 1977.35  4999.1 1977.35  4999.6 1977.85  5014.1 1978.36  5028.3 1984.94
  5042.4 1992.72  5056.5 1999.43  5084.8 2008.66  5099.0 2014.19  5127.3 2022.56
  5153.1 2031.52  5169.7 2036.61  5198.0 2046.79  5208.6 2049.75  5212.1 2049.75
#Mann=5,-1,0
  4717.1     0.1       0  4771.9    0.07       0  4993.3    0.05       0
  4999.6    0.07       0  5153.1     0.1       0
Bank Sta=4993.3,4999.6
Exp/Cntr=0.3,0.1

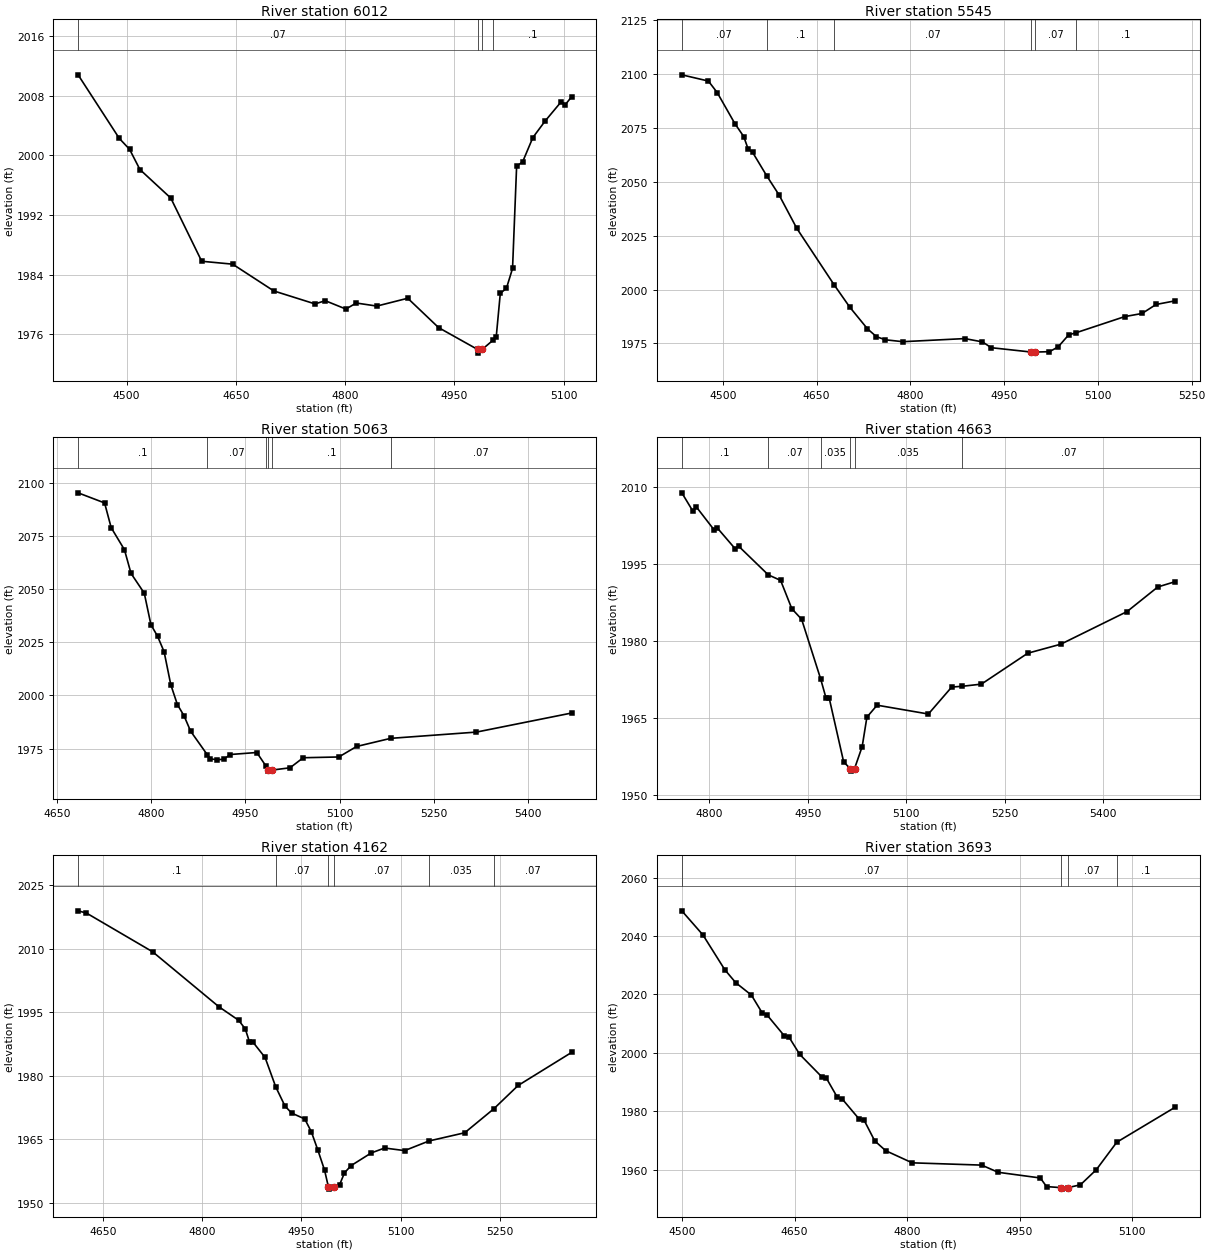
Type RM Length L Ch R = 1,6012,467,467,467
BEGIN DESCRIPTION:
Pecan Creek 12.0
END DESCRIPTION:
XS GIS Cut Line= 3
      1856174.98     13901024.98      1856575.00     13901425.00
      1856674.98     13901474.99
#Sta/Elev= 30
  4433.4 2010.81  4490.0 2002.28  4504.1 2000.82  4518.3 1998.11  4560.7 1994.28
  4603.1 1985.81  4645.6 1985.42  4702.1 1981.83  4758.7 1980.09  4772.8 1980.52
  4801.1 1979.40  4815.3 1980.21  4843.6 1979.80  4886.0 1980.85  4928.4 1976.91
  4981.8 1973.99  4982.3 1973.49  4988.2 1973.99  5003.3 1975.24  5007.5 1975.68
  5013.1 1981.51  5021.5 1982.18  5029.9 1984.85  5035.5 1998.55  5043.8 1999.15
  5057.8 2002.40  5074.6 2004.61  5096.9 2007.22  5102.5 2006.83  5110.9 2007.86
#Mann=4,-1,0
  4433.4    0.07       0  4981.8    0.05       0  4988.2    0.07       0
  5003.3     0.1       0
Bank Sta=4981.8,4988.2
Exp/Cntr=0.3,0.1

Type RM Length L Ch R = 1,5545,482,482,482
BEGIN DESCRIPTION:
Pecan Creek 11.0
END DESCRIPTION:
XS GIS Cut Line= 3
      1855724.97     13900974.97      1856125.00     13901375.00
      1856224.98     13901574.97
#Sta/Elev= 30
  4434.4 2099.68  4476.9 2096.79  4491.0 2091.45  4519.3 2077.02  4533.4 2071.04
  4540.5 2065.24  4547.6 2063.71  4570.3 2052.76  4590.0 2043.90  4618.3 2028.42
  4678.3 2002.10  4703.1 1991.83  4731.4 1981.78  4745.6 1978.17  4759.7 1976.71
  4788.0 1975.82  4887.0 1977.26  4915.3 1975.72  4929.4 1973.03  4993.3 1971.01
  4993.8 1970.51  4999.8 1971.01  5022.5 1971.18  5036.5 1973.45  5053.2 1978.99
  5065.3 1980.00  5142.7 1987.45  5170.6 1988.92  5193.0 1993.10  5223.7 1994.79
#Mann=6,-1,0
  4434.4    0.07       0  4570.3     0.1       0  4678.3    0.07       0
  4993.3    0.05       0  4999.8    0.07       0  5065.3     0.1       0
Bank Sta=4993.3,4999.8
Exp/Cntr=0.3,0.1

Type RM Length L Ch R = 1,5063,400,400,400
BEGIN DESCRIPTION:
Pecan Creek 10.0
END DESCRIPTION:
XS GIS Cut Line= 3
      1855574.99     13901124.98      1855675.00     13901425.00
      1856016.26     13901747.52
#Sta/Elev= 30
  4683.7 2095.19  4725.9 2090.44  4736.4 2078.82  4757.5 2068.48  4768.0 2057.33
  4789.1 2048.05  4799.7 2033.24  4810.2 2027.84  4820.7 2020.52  4831.3 2005.07
  4841.8 1995.75  4852.4 1990.45  4862.9 1983.22  4889.7 1972.06  4894.5 1970.23
  4905.1 1969.81  4915.6 1970.04  4926.2 1972.27  4968.3 1973.21  4983.2 1966.70
  4986.1 1964.96  4986.6 1964.46  4992.7 1964.96  5021.2 1966.03  5042.2 1970.75
  5098.9 1971.11  5127.2 1976.04  5181.5 1979.86  5318.1 1982.80  5469.5 1991.75
#Mann=6,-1,0
  4683.7     0.1       0  4889.7    0.07       0  4983.2     0.1       0
  4986.1    0.05       0  4992.7     0.1       0  5181.5    0.07       0
Bank Sta=4986.1,4992.7
Exp/Cntr=0.3,0.1

Type RM Length L Ch R = 1,4663,501,501,501
BEGIN DESCRIPTION:
Pecan Creek 9.0
END DESCRIPTION:
XS GIS Cut Line= 4
      1855394.23     13901505.59      1855463.19     13901719.17
      1855544.20     13901757.70      1855977.82     13901813.21
#Sta/Elev= 30
  4758.3 2008.81  4775.3 2005.21  4780.5 2006.05  4807.3 2001.62  4812.6 2001.93
  4839.3 1997.95  4844.6 1998.45  4889.9 1992.84  4908.7 1991.76  4925.8 1986.24
  4940.7 1984.19  4969.5 1972.65  4977.9 1968.83  4982.7 1968.83  5004.7 1956.41
  5014.7 1955.12  5015.2 1954.62  5021.3 1955.12  5032.9 1959.40  5040.1 1965.13
  5055.6 1967.46  5133.7 1965.74  5169.2 1970.99  5185.2 1971.14  5214.4 1971.56
  5285.0 1977.58  5335.4 1979.34  5436.2 1985.69  5483.0 1990.48  5509.6 1991.52
#Mann=6,-1,0
  4758.3     0.1       0  4889.9    0.07       0  4969.5   0.035       0
  5014.7   0.035       0  5021.3   0.035       0  5185.2    0.07       0
Bank Sta=5014.7,5021.3
Exp/Cntr=0.3,0.1

Type RM Length L Ch R = 1,4162,469,469,469
BEGIN DESCRIPTION:
Pecan Creek 8.0
END DESCRIPTION:
XS GIS Cut Line= 4
      1855132.34     13902162.72      1855392.76     13902175.00
      1855525.00     13902175.00      1855875.00     13902125.00
#Sta/Elev= 30
  4612.1 2018.91  4624.8 2018.38  4724.9 2009.24  4825.0 1996.29  4855.0 1993.08
  4865.0 1991.05  4871.4 1987.97  4876.4 1987.97  4895.0 1984.30  4911.1 1977.37
  4925.0 1972.87  4935.0 1971.20  4955.0 1969.80  4965.0 1966.76  4975.0 1962.37
  4985.0 1957.70  4990.8 1953.74  4991.3 1953.24  4999.2 1953.74  5007.6 1954.23
  5015.1 1957.09  5025.2 1958.80  5055.6 1961.78  5075.8 1962.94  5106.1 1962.33
  5142.9 1964.60  5197.0 1966.54  5241.0 1972.19  5277.8 1977.70  5358.6 1985.49
#Mann=6,-1,0
  4612.1     0.1       0  4911.1    0.07       0  4990.8    0.05       0
  4999.2    0.07       0  5142.9   0.035       0  5241.0    0.07       0
Bank Sta=4990.8,4999.2
Exp/Cntr=0.3,0.1

Type RM Length L Ch R = 1,3693,466,466,466
BEGIN DESCRIPTION:
Pecan Creek 7.0
END DESCRIPTION:
XS GIS Cut Line= 3
      1855324.96     13902875.03      1855725.00     13902575.00
      1855875.04     13902625.01
#Sta/Elev= 30
  4499.5 2048.65  4527.7 2040.38  4556.8 2028.48  4571.4 2024.03  4592.3 2019.78
  4606.8 2013.63  4613.1 2012.99  4636.0 2005.88  4642.3 2005.44  4656.8 1999.45
  4686.0 1991.82  4692.3 1991.32  4706.8 1984.81  4713.1 1984.28  4736.0 1977.31
  4742.3 1977.07  4756.8 1969.83  4771.4 1966.47  4806.8 1962.30  4899.5 1961.52
  4921.4 1959.06  4977.7 1957.11  4986.0 1954.16  5005.8 1953.79  5006.3 1953.29
  5014.3 1953.79  5031.2 1954.77  5052.3 1959.92  5079.7 1969.37  5157.7 1981.38
#Mann=4,-1,0
  4499.5    0.07       0  5005.8    0.05       0  5014.3    0.07       0
  5079.7     0.1       0
Bank Sta=5005.8,5014.3
Exp/Cntr=0.3,0.1

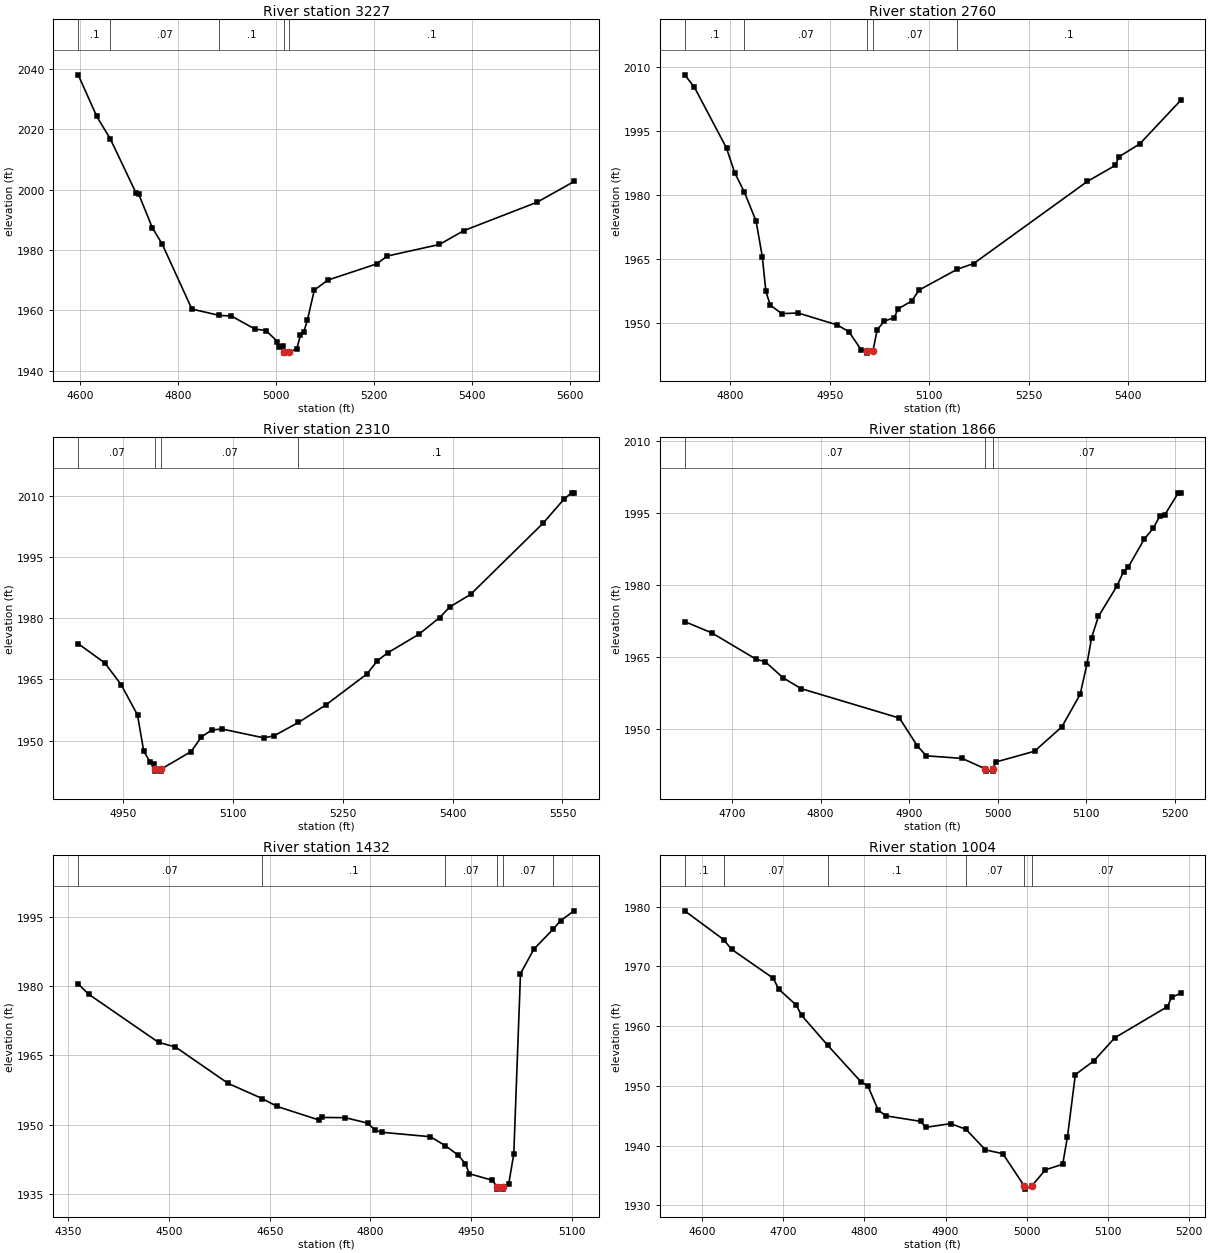
Type RM Length L Ch R = 1,3227,467,467,467
BEGIN DESCRIPTION:
Pecan Creek 6.0
END DESCRIPTION:
XS GIS Cut Line= 3
      1855375.02     13903075.00      1855775.00     13903025.00
      1856240.28     13902633.14
#Sta/Elev= 30
  4596.9 2038.12  4634.7 2024.33  4662.4 2016.88  4715.3 1998.78  4720.3 1998.56
  4748.0 1987.43  4768.2 1982.00  4828.7 1960.47  4884.2 1958.38  4909.3 1958.15
  4957.2 1953.85  4979.8 1953.35  5003.3 1949.69  5007.1 1947.78  5013.7 1948.28
  5017.0 1946.36  5017.5 1945.86  5025.8 1946.36  5042.3 1947.09  5050.0 1951.77
  5056.6 1952.71  5064.3 1956.83  5078.4 1966.77  5106.0 1970.07  5206.1 1975.47
  5226.9 1978.04  5333.6 1981.88  5383.0 1986.45  5532.5 1995.87  5608.3 2002.77
#Mann=5,-1,0
  4596.9     0.1       0  4662.4    0.07       0  4884.2     0.1       0
  5017.0    0.05       0  5025.8     0.1       0
Bank Sta=5017,5025.8
Exp/Cntr=0.3,0.1

Type RM Length L Ch R = 1,2760,450,450,450
BEGIN DESCRIPTION:
Pecan Creek 5.0
END DESCRIPTION:
XS GIS Cut Line= 3
      1855575.02     13903574.99      1855825.00     13903475.00
      1856278.14     13903319.84
#Sta/Elev= 30
  4731.2 2008.20  4746.0 2005.26  4794.4 1991.02  4806.6 1985.29  4821.1 1980.77
  4838.9 1973.96  4848.3 1965.65  4853.7 1957.48  4860.4 1954.24  4877.9 1952.28
  4902.2 1952.43  4961.4 1949.63  4978.9 1948.06  4997.7 1943.75  5006.4 1943.53
  5006.9 1943.03  5015.2 1943.53  5021.6 1948.50  5032.1 1950.49  5047.4 1951.37
  5053.3 1953.41  5073.4 1955.19  5085.0 1957.81  5142.4 1962.67  5167.2 1964.01
  5338.7 1983.24  5381.0 1987.00  5386.3 1989.00  5417.6 1992.01  5479.4 2002.20
#Mann=5,-1,0
  4731.2     0.1       0  4821.1    0.07       0  5006.4    0.05       0
  5015.2    0.07       0  5142.4     0.1       0
Bank Sta=5006.4,5015.2
Exp/Cntr=0.3,0.1

Type RM Length L Ch R = 1,2310,444,444,444
BEGIN DESCRIPTION:
Pecan Creek 4.0
END DESCRIPTION:
XS GIS Cut Line= 3
      1855875.02     13903924.99      1855975.00     13903875.00
      1856375.03     13903474.97
#Sta/Elev= 30
  4888.5 1973.76  4924.8 1969.04  4947.2 1963.71  4969.5 1956.28  4977.9 1947.50
  4986.3 1944.82  4991.9 1944.20  4993.0 1943.01  4993.5 1942.51  5001.4 1942.51
  5001.9 1943.01  5042.7 1947.31  5056.8 1950.88  5071.0 1952.61  5085.1 1952.83
  5141.7 1950.68  5155.8 1951.15  5189.4 1954.45  5226.6 1958.71  5283.1 1966.36
  5297.3 1969.61  5311.4 1971.53  5353.8 1976.06  5382.1 1980.15  5396.3 1982.80
  5424.5 1985.84  5523.5 2003.30  5551.8 2009.14  5562.4 2010.76  5566.0 2010.76
#Mann=4,-1,0
  4888.5    0.07       0  4993.0    0.05       0  5001.9    0.07       0
  5189.4     0.1       0
Bank Sta=4993,5001.9
Exp/Cntr=0.3,0.1

Type RM Length L Ch R = 1,1866,434,434,434
BEGIN DESCRIPTION:
Pecan Creek 3.0
END DESCRIPTION:
XS GIS Cut Line= 3
      1855975.00     13904175.00      1856325.00     13904125.00
      1856524.99     13904075.00
#Sta/Elev= 30
  4646.7 1972.44  4677.0 1970.13  4727.5 1964.59  4737.6 1964.09  4757.8 1960.74
  4778.0 1958.49  4889.1 1952.35  4909.3 1946.54  4919.4 1944.49  4959.8 1943.95
  4985.7 1941.80  4986.2 1941.30  4994.2 1941.30  4994.7 1941.80  4997.7 1943.19
  5041.5 1945.44  5072.4 1950.54  5093.0 1957.28  5100.8 1963.69  5105.9 1969.09
  5113.6 1973.51  5134.3 1979.78  5142.0 1982.86  5147.1 1983.73  5165.2 1989.59
  5175.5 1991.89  5183.2 1994.51  5188.4 1994.65  5203.8 1999.27  5206.4 1999.27
#Mann=3,-1,0
  4646.7    0.07       0  4985.7    0.05       0  4994.7    0.07       0
Bank Sta=4985.7,4994.7
Exp/Cntr=0.3,0.1

Type RM Length L Ch R = 1,1432,428,428,428
BEGIN DESCRIPTION:
Pecan Creek 2.0
END DESCRIPTION:
XS GIS Cut Line= 3
      1855859.87     13904300.60      1856475.00     13904475.00
      1856575.03     13904475.00
#Sta/Elev= 30
  4364.5 1980.44  4380.2 1978.22  4484.2 1967.84  4509.5 1966.83  4588.1 1958.97
  4638.9 1955.69  4660.9 1954.00  4723.2 1951.08  4728.7 1951.62  4762.6 1951.57
  4796.0 1950.40  4806.9 1948.91  4816.8 1948.42  4889.5 1947.46  4911.5 1945.55
  4931.1 1943.47  4941.5 1941.65  4947.8 1939.45  4981.7 1938.07  4989.0 1936.64
  4989.5 1936.14  4997.5 1936.14  4998.0 1936.64  5006.4 1937.33  5013.9 1943.71
  5023.9 1982.67  5043.9 1987.98  5072.4 1992.24  5083.9 1994.15  5103.9 1996.24
#Mann=6,-1,0
  4364.5    0.07       0  4638.9     0.1       0  4911.5    0.07       0
  4989.0    0.05       0  4998.0    0.07       0  5072.4     0.1       0
Bank Sta=4989,4998
Exp/Cntr=0.3,0.1

Type RM Length L Ch R = 1,1004,502,502,502
BEGIN DESCRIPTION:
Pecan Creek 1.0
END DESCRIPTION:
XS GIS Cut Line= 3
      1855811.50     13904499.70      1856236.70     13904754.99
      1856350.63     13904738.33
#Sta/Elev= 30
  4578.6 1979.28  4626.5 1974.47  4636.3 1972.85  4687.7 1968.00  4694.6 1966.15
  4716.0 1963.51  4722.7 1961.78  4754.8 1956.78  4795.7 1950.68  4804.3 1949.98
  4817.1 1945.91  4826.8 1944.96  4869.5 1944.04  4875.4 1943.04  4906.4 1943.66
  4925.2 1942.71  4949.2 1939.27  4970.6 1938.63  4997.2 1933.20  4997.7 1932.70
  5006.2 1933.20  5023.0 1935.93  5044.4 1936.86  5050.3 1941.49  5060.0 1951.87
  5082.9 1954.18  5108.6 1958.03  5173.5 1963.25  5178.5 1964.78  5189.7 1965.48
#Mann=6,-1,0
  4578.6     0.1       0  4626.5    0.07       0  4754.8     0.1       0
  4925.2    0.07       0  4997.2    0.05       0  5006.2    0.07       0
Bank Sta=4997.2,5006.2
Exp/Cntr=0.3,0.1

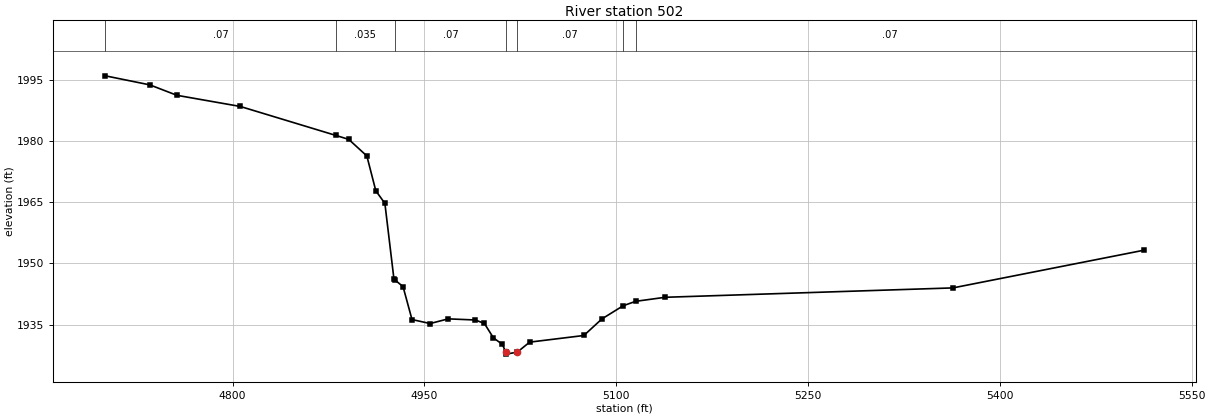
Type RM Length L Ch R = 1,502,0,0,0
BEGIN DESCRIPTION:
Pecan Creek 0.0
END DESCRIPTION:
XS GIS Cut Line= 3
      1855564.32     13904766.52      1855887.25     13905091.19
      1856225.76     13904987.03
#Sta/Elev= 30
  4700.5 1996.00  4735.3 1993.78  4756.5 1991.22  4806.0 1988.49  4880.5 1981.41
  4890.8 1980.42  4905.0 1976.35  4912.0 1967.81  4919.1 1964.72  4926.2 1946.12
  4927.2 1945.87  4933.3 1944.31  4940.3 1936.23  4954.5 1935.25  4968.6 1936.40
  4989.8 1936.12  4996.9 1935.28  5004.0 1931.73  5011.0 1930.14  5013.6 1928.25
  5014.1 1927.75  5022.7 1928.25  5032.3 1930.69  5074.7 1932.32  5088.8 1936.38
  5105.4 1939.61  5115.2 1940.70  5138.3 1941.69  5363.3 1943.99  5512.6 1953.23
#Mann=7,-1,0
  4700.5    0.07       0  4880.5   0.035       0  4927.2    0.07       0
  5013.6    0.05       0  5022.7    0.07       0  5105.4   0.035       0
  5115.2    0.07       0
Bank Sta=5013.6,5022.7
Exp/Cntr=0.3,0.1

Chan Stop Cuts=-1