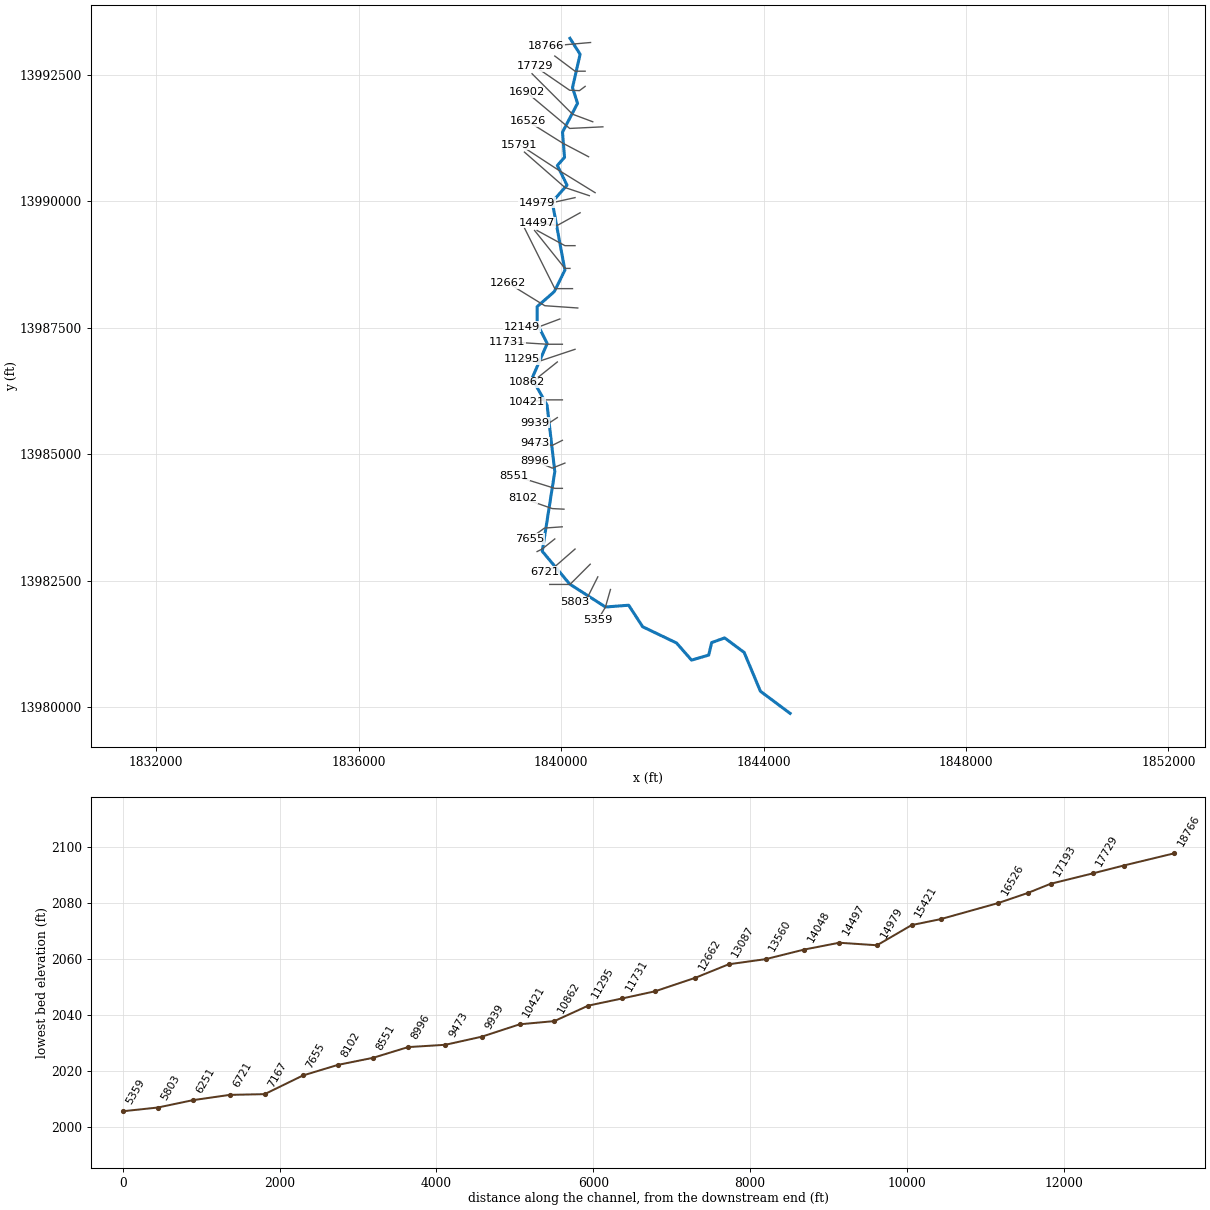
--- Rough Creek.prj (project) ---

Proj Title=Rough Creek Base Level Engineering
Current Plan=p01
Default Exp/Contr=0.3,0.1
English Units
Geom File=g01
Flow File=f01
Plan File=p01
Y Axis Title=Elevation
X Axis Title(PF)=Main Channel Distance
X Axis Title(XS)=Station
BEGIN DESCRIPTION:
Rough Creek
END DESCRIPTION:
DSS Export Rating Curves= 0
DSS Export Rating Curve Sorted= 0
DSS Export Volume Flow Curves= 0
DXF OffsetX= 0
DXF OffsetY= 0
DXF ScaleX= 1
DXF ScaleY= 10

--- Rough Creek.p01 (plan) ---

Plan Title=Multiple Run
Short Identifier=Multiple
Geom File=g01
Flow File=f01
Subcritical Flow
K Sum by GR= 0
Std Step Tol= 0.01
Critical Tol= 0.01
Num of Std Step Trials= 20
Max Error Tol= 0.3
Flow Tol Ratio= 0.001
Split Flow NTrial= 30
Split Flow Tol= 0.02
Split Flow Ratio= 0.02
Log Output Level= 0
Friction Slope Method= 1
Unsteady Friction Slope Method= 2
Unsteady Bridges Friction Slope Method= 1
Parabolic Critical Depth
Global Vel Dist=  1 , 1 , 1
Global Log Level= 0
CheckData=True
Encroach Param= -1, 0, 0, 0
BEGIN DESCRIPTION:
Multiple Run
END DESCRIPTION:

--- Rough Creek.f01 (steady flow) ---

Flow Title=Multiple
Number of Profiles=7
Profile Names=10-year,25-year,50-year,1pct_min,100-year,1pct_plu,500-year
River Rch & RM= Rough Creek,Reach-1,18766
    1841    3222    4566    3118    6221   12413   11429
River Rch & RM= Rough Creek,Reach-1,14048
    1833    3203    4533    3091    6168   12307   11301
River Rch & RM= Rough Creek,Reach-1,12662
    2327    4110    5856    4018    8016   15995   14866
River Rch & RM= Rough Creek,Reach-1,8551
    2530    4479    6393    4392    8762   17483   16291
River Rch & RM= Rough Creek,Reach-1,2239
    2843    5066    7262    5009    9995   19942   18739
Boundary for River Rch & Prof#=Rough Creek,Reach-1,1
Up Type=0
Dn Type=3
Dn Slope=0.005
Boundary for River Rch & Prof#=Rough Creek,Reach-1,2
Up Type=0
Dn Type=3
Dn Slope=0.005
Boundary for River Rch & Prof#=Rough Creek,Reach-1,3
Up Type=0
Dn Type=3
Dn Slope=0.005
Boundary for River Rch & Prof#=Rough Creek,Reach-1,4
Up Type=0
Dn Type=3
Dn Slope=0.005
Boundary for River Rch & Prof#=Rough Creek,Reach-1,5
Up Type=0
Dn Type=3
Dn Slope=0.005
Boundary for River Rch & Prof#=Rough Creek,Reach-1,6
Up Type=0
Dn Type=3
Dn Slope=0.005
Boundary for River Rch & Prof#=Rough Creek,Reach-1,7
Up Type=0
Dn Type=3
Dn Slope=0.005

--- Rough Creek.g01 (geometry) ---

Geom Title=Existing Conditions
Program Version=4.10

River Reach=Rough Creek     ,Reach-1
Reach XY= 30
        1840175.       13993225.      1840375.09     13992909.78
       1840224.6       13992250.      1840324.62     13991940.27
      1840026.98     13991369.33      1840067.23     13990871.59
      1839924.89     13990709.64      1840117.01     13990321.65
      1839824.28     13989990.06      1840074.49     13988640.22
      1839864.23      13988215.3      1839526.89     13987919.22
      1839527.01     13987580.68      1839725.09     13987190.22
      1839424.58       13986500.      1839722.76     13985969.07
      1839874.94     13984654.97      1839627.25     13983080.93
      1840168.81     13982432.86      1840876.47     13981978.56
      1841335.06      13982013.9      1841611.33     13981588.23
      1842281.07     13981266.87      1842576.65     13980928.11
      1842916.72     13981028.06        1842975.       13981275.
      1843231.19     13981367.18      1843616.85     13981081.07
      1843938.62     13980311.78        1844525.       13979875.

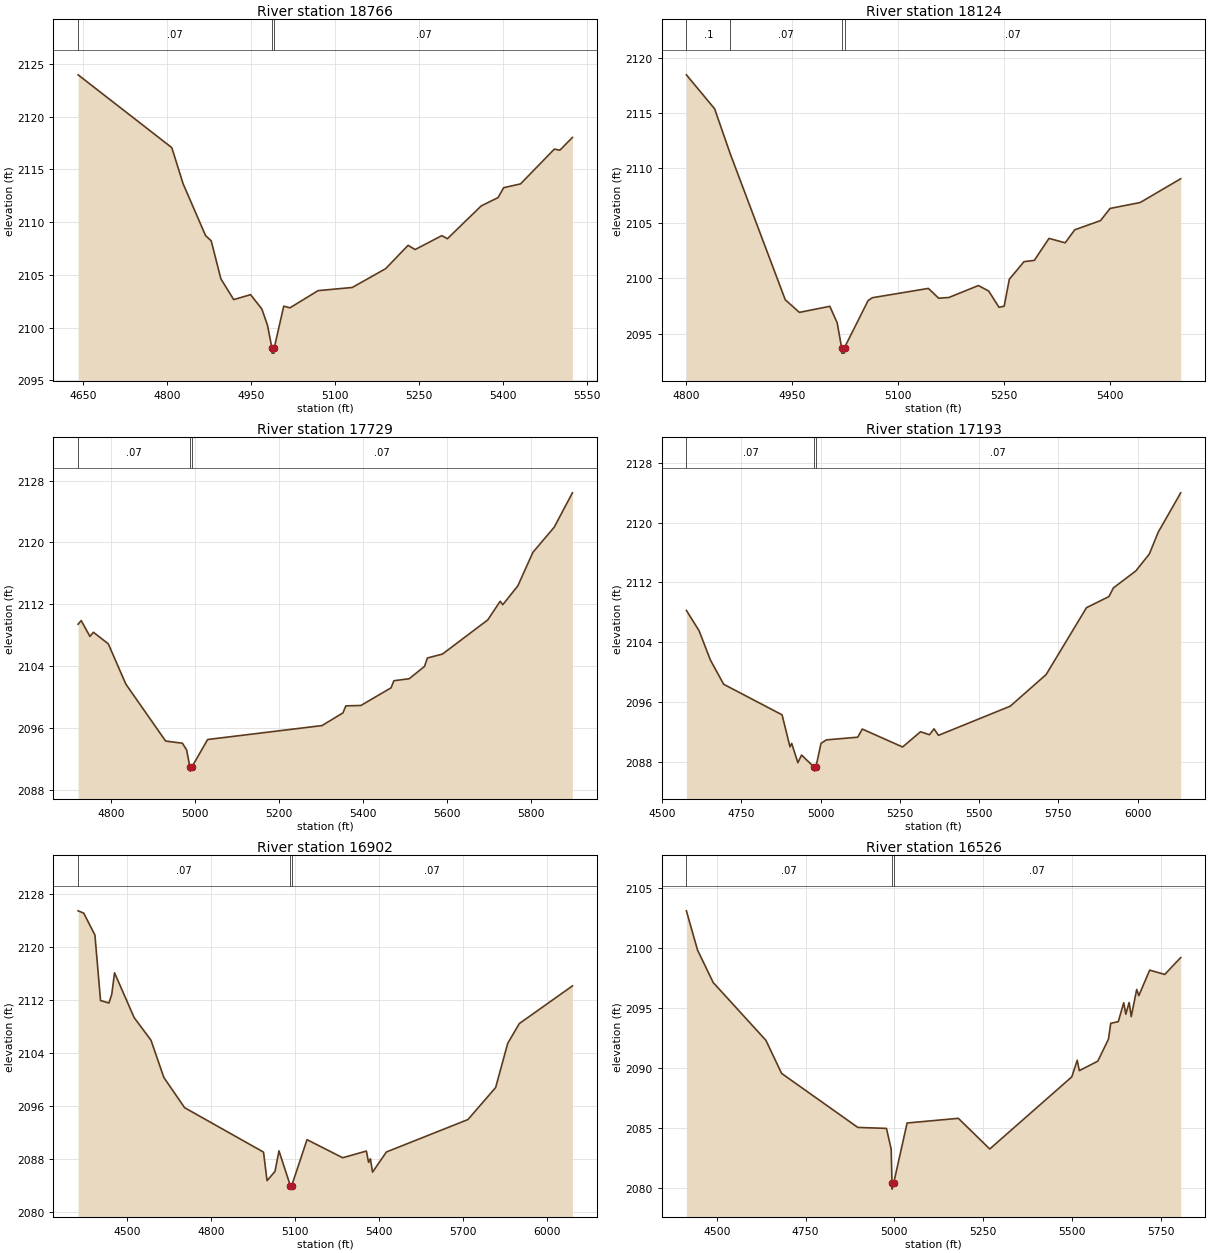
Type RM Length L Ch R = 1 ,18766   ,642,642,642
BEGIN DESCRIPTION:
Rough Creek 40.0
END DESCRIPTION:
XS GIS Cut Line= 2
       1840581.6     13993142.54       1839702.8     13993065.18
#Sta/Elev= 30
  4641.8 2123.98    4809 2117.07  4829.1 2113.65  4869.3 2108.72  4879.3 2108.23
  4896.6 2104.62  4919.5 2102.65  4949.6 2103.12  4969.7 2101.76  4979.7 2100.23
  4987.7 2098.07  4987.9 2097.57  4991.5 2097.57  4991.8 2098.07  5008.8 2102.03
  5019.9 2101.87  5070.1  2103.5  5131.1  2103.8  5190.5 2105.58  5230.7  2107.8
  5243.3  2107.4  5290.9 2108.72  5300.9 2108.43  5361.2 2111.54  5391.3 2112.33
  5401.3 2113.27  5431.4 2113.63  5491.7 2116.93  5501.7 2116.83    5524 2118.04
#Mann= 3 ,-1 , 0
  4641.8     .07       0  4987.7     .05       0  4991.8     .07       0
Bank Sta=4987.7,4991.8
XS Rating Curve= 0 ,0
Exp/Cntr=0.3,0.1

Type RM Length L Ch R = 1 ,18124   ,395,395,395
BEGIN DESCRIPTION:
Rough Creek 39.0
END DESCRIPTION:
XS GIS Cut Line= 3
      1840474.97       13992575.        1840275.       13992575.
      1839874.98     13992875.02
#Sta/Elev= 30
    4800 2118.44    4840 2115.36  4861.9 2111.32    4940 2098.07    4960 2096.93
  5003.1 2097.48  5013.5 2095.99  5019.8 2093.74    5020 2093.24  5023.6 2093.24
  5023.9 2093.74  5057.3    2098  5063.5 2098.26  5142.7  2099.1  5157.3 2098.21
  5171.8 2098.28  5213.5 2099.36  5228.1 2098.86  5242.7 2097.39    5250 2097.49
  5257.3 2099.93  5278.1 2101.52  5292.7 2101.64  5313.5 2103.63  5336.4 2103.23
    5350 2104.41  5386.4 2105.24    5400 2106.34  5442.7 2106.88    5500 2109.03
#Mann= 4 ,-1 , 0
    4800      .1       0  4861.9     .07       0  5019.8     .05       0
  5023.9     .07       0
Bank Sta=5019.8,5023.9
XS Rating Curve= 0 ,0
Exp/Cntr=0.3,0.1

Type RM Length L Ch R = 1 ,17729   ,536,536,536
BEGIN DESCRIPTION:
Rough Creek 38.0
END DESCRIPTION:
XS GIS Cut Line= 4
      1840474.97     13992274.98      1840362.42     13992190.57
      1840168.07     13992198.51      1839474.97     13992675.02
#Sta/Elev= 30
  4721.6 2109.43  4728.9  2109.9  4749.7 2107.85    4758 2108.39  4793.4 2106.89
  4835.1 2101.69  4929.8 2094.32  4969.8 2094.04  4979.8 2093.17  4987.7 2090.93
    4988 2090.43  4991.9 2090.93  5029.8 2094.52  5301.9 2096.32  5351.8 2097.96
  5358.7 2098.87  5394.5 2098.92  5466.2  2101.2  5473.1 2102.12  5509.5 2102.38
  5545.9 2103.97  5552.8 2105.06  5588.7 2105.57  5696.3 2109.98    5726  2112.4
  5732.1 2111.95    5768 2114.39  5803.8 2118.72  5854.6 2121.98  5897.9 2126.42
#Mann= 3 ,-1 , 0
  4721.6     .07       0  4987.7     .05       0  4991.9     .07       0
Bank Sta=4987.7,4991.9
XS Rating Curve= 0 ,0
Exp/Cntr=0.3,0.1

Type RM Length L Ch R = 1 ,17193   ,291,291,291
BEGIN DESCRIPTION:
Rough Creek 37.0
END DESCRIPTION:
XS GIS Cut Line= 3
      1840624.98     13991575.01        1840225.       13991725.
      1839424.97     13992525.03
#Sta/Elev= 30
    4577 2108.24    4617 2105.52  4652.6 2101.61  4694.5 2098.36  4878.7 2094.27
  4903.6 2089.99    4909 2090.45  4928.5 2087.87  4940.1 2088.89  4980.5 2087.24
  4980.8 2086.74  4985.1 2087.24  5001.5 2090.46  5018.3 2090.92  5117.3 2091.28
  5131.5 2092.37  5258.7 2089.97  5315.3 2092.01  5343.6 2091.61  5357.7  2092.4
  5371.9 2091.53  5598.2 2095.43  5711.3 2099.66  5838.6 2108.61  5909.3 2110.09
  5923.4 2111.25  5994.1 2113.52  6036.6 2115.78  6064.8 2118.71  6135.6 2123.97
#Mann= 3 ,-1 , 0
    4577     .07       0  4980.5     .05       0  4985.1     .07       0
Bank Sta=4980.5,4985.1
XS Rating Curve= 0 ,0
Exp/Cntr=0.3,0.1

Type RM Length L Ch R = 1 ,16902   ,376,376,376
BEGIN DESCRIPTION:
Rough Creek 36.0
END DESCRIPTION:
XS GIS Cut Line= 3
      1840824.96       13991475.      1840168.96     13991442.94
      1839319.51     13992156.08
#Sta/Elev= 30
  4325.5  2125.5  4345.5 2125.15  4385.5 2121.84  4405.6 2111.95  4435.6 2111.58
  4445.6 2112.88  4455.6 2116.14  4525.7 2109.37  4585.8 2105.96  4631.8 2100.33
  4705.9 2095.77  4987.8 2089.06  5000.5 2084.75  5028.8 2086.15  5043.1 2089.25
  5083.7 2083.97    5084 2083.47  5088.3 2083.97  5143.2 2090.94  5270.7 2088.21
  5355.3 2089.22  5363.1 2087.51  5369.6 2088.05  5377.4 2086.04  5426.8 2089.08
  5718.2 2093.98  5817.1 2098.81    5860 2105.46  5901.6 2108.47  6091.4 2114.16
#Mann= 3 ,-1 , 0
  4325.5     .07       0  5083.7     .05       0  5088.3     .07       0
Bank Sta=5083.7,5088.3
XS Rating Curve= 0 ,0
Exp/Cntr=0.3,0.1

Type RM Length L Ch R = 1 ,16526   ,735,735,735
BEGIN DESCRIPTION:
Rough Creek 35.0
END DESCRIPTION:
XS GIS Cut Line= 3
      1840542.99     13990882.96      1840028.24     13991154.33
      1839342.75     13991584.34
#Sta/Elev= 30
  4414.7 2103.12    4446 2099.85    4490 2097.14  4638.5 2092.31  4682.6 2089.55
  4897.2 2085.04  4977.7 2084.96    4991 2083.23  4993.3 2080.39  4993.6 2079.89
    4998 2080.39  5035.8 2085.41    5180  2085.8  5268.4 2083.24  5499.3 2089.26
  5514.6 2090.65  5520.5 2089.78  5572.4 2090.57  5602.5 2092.41  5608.9 2093.73
  5630.1 2093.87  5645.4 2095.45  5651.3 2094.49  5660.7 2095.47  5666.6 2094.29
    5682 2096.56  5687.9 2096.04  5718.5 2098.17  5760.9 2097.81  5805.8 2099.22
#Mann= 3 ,-1 , 0
  4414.7     .07       0  4993.3     .05       0    4998     .07       0
Bank Sta=4993.3,4998
XS Rating Curve= 0 ,0
Exp/Cntr=0.3,0.1

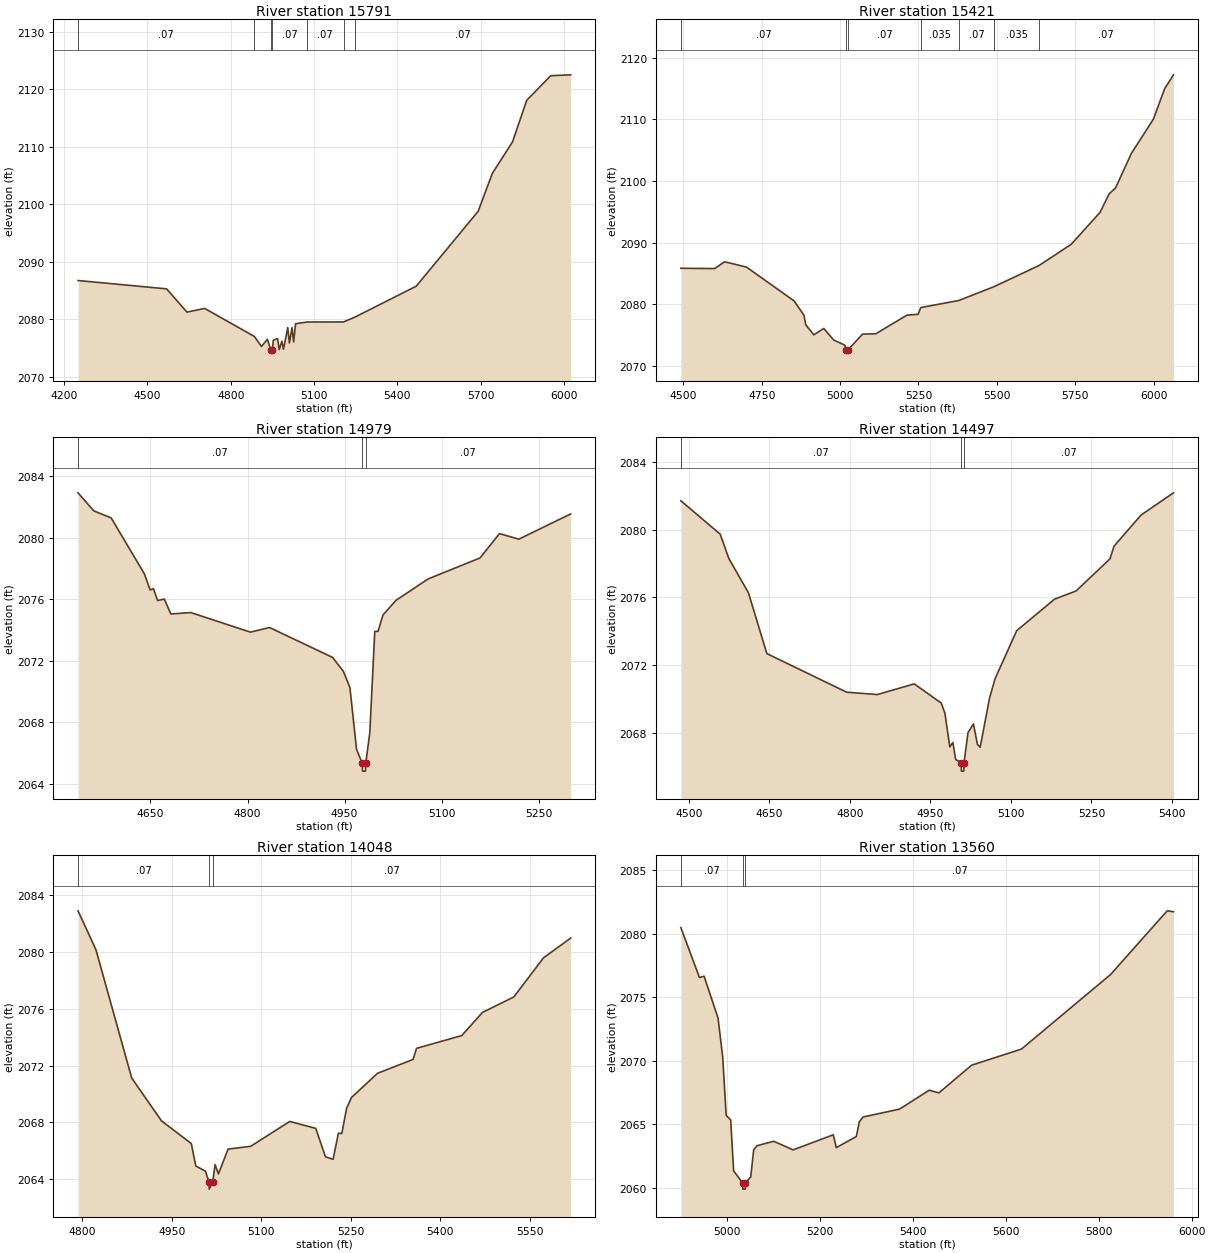
Type RM Length L Ch R = 1 ,15791   ,370,370,370
BEGIN DESCRIPTION:
Rough Creek 34.0
END DESCRIPTION:
XS GIS Cut Line= 3
      1840671.49      13990172.6      1839935.82     13990626.81
      1839175.01       13991125.
#Sta/Elev= 30
  4250.3 2086.77  4569.2 2085.32  4642.5 2081.28  4706.3 2081.92  4885.4 2077.04
  4910.9 2075.31  4932.2 2076.55  4944.9 2074.65  4945.3 2074.15  4950.1 2074.65
  4953.4 2076.39  4968.8 2076.68  4974.8 2074.76  4984.2 2076.21  4990.1 2074.83
  5005.5 2078.58  5011.4 2075.92  5020.9 2078.58  5026.7  2076.1  5033.6 2079.26
  5074.8 2079.56  5206.6 2079.57  5247.4 2080.41    5468 2085.78  5691.1  2098.8
  5742.4 2105.41  5814.8 2110.85    5866 2118.09  5952.6 2122.37  6024.3 2122.52
#Mann= 7 ,-1 , 0
  4250.3     .07       0  4885.4     .07       0  4944.9     .05       0
  4950.1     .07       0  5074.8     .07       0  5206.6    .035       0
  5247.4     .07       0
Bank Sta=4944.9,4950.1
XS Rating Curve= 0 ,0
Exp/Cntr=0.3,0.1

Type RM Length L Ch R = 1 ,15421   ,442,442,442
BEGIN DESCRIPTION:
Rough Creek 33.0
END DESCRIPTION:
XS GIS Cut Line= 3
      1840557.37     13990113.04        1840075.       13990275.
      1839274.96     13990975.03
#Sta/Elev= 30
  4491.8 2085.81  4599.8 2085.77  4631.4 2086.87  4701.1 2086.01    4853 2080.52
  4884.6 2078.18  4890.3 2076.63  4916.2    2075  4947.9 2076.04  4979.5 2074.16
  5014.4 2073.34  5019.4 2072.53  5019.8 2072.03  5024.6 2072.53  5071.3 2075.11
  5114.1 2075.18  5213.2  2078.2  5248.8 2078.34  5257.4 2079.43  5378.8 2080.58
  5490.7 2082.82  5634.7 2086.26  5737.6 2089.72  5829.7 2094.92  5858.2 2097.89
    5879 2098.88  5929.4 2104.48  5999.6 2110.04  6035.7 2115.01  6063.7 2117.24
#Mann= 7 ,-1 , 0
  4491.8     .07       0  5019.4     .05       0  5024.6     .07       0
  5257.4    .035       0  5378.8     .07       0  5490.7    .035       0
  5634.7     .07       0
Bank Sta=5019.4,5024.6
XS Rating Curve= 0 ,0
Exp/Cntr=0.3,0.1

Type RM Length L Ch R = 1 ,14979   ,482,482,482
BEGIN DESCRIPTION:
Rough Creek 32.0
END DESCRIPTION:
XS GIS Cut Line= 3
        1840275.       13990075.        1839825.       13989975.
      1839524.98       13989975.
#Sta/Elev= 30
  4538.2 2082.92  4562.5 2081.75  4589.4 2081.29  4640.6 2077.66  4649.6 2076.61
  4654.7 2076.69  4661.1 2075.92  4671.4 2076.02  4681.6 2075.05  4712.4 2075.14
  4804.5 2073.87    4834 2074.17  4931.3 2072.23    4948 2071.33  4958.2 2070.27
  4968.4 2066.26  4977.3 2065.34  4977.7 2064.84  4982.2 2064.84  4982.6 2065.34
  4988.9 2067.33  4996.6 2073.92  5001.7 2073.92  5009.2 2074.98  5029.2 2075.93
  5079.2 2077.33  5159.2 2078.69  5189.2 2080.27  5219.2 2079.91  5299.2 2081.55
#Mann= 3 ,-1 , 0
  4538.2     .07       0  4977.3     .05       0  4982.6     .07       0
Bank Sta=4977.3,4982.6
XS Rating Curve= 0 ,0
Exp/Cntr=0.3,0.1

Type RM Length L Ch R = 1 ,14497   ,449,449,449
BEGIN DESCRIPTION:
Rough Creek 31.0
END DESCRIPTION:
XS GIS Cut Line= 3
      1840375.04     13989775.02        1839925.       13989525.
      1839525.04     13989574.99
#Sta/Elev= 30
  4484.9  2081.7  4558.2 2079.73  4574.2  2078.3  4610.8 2076.27  4645.1 2072.68
  4793.8  2070.4    4851 2070.26  4919.7 2070.89    4970 2069.76  4976.9 2069.16
    4986 2067.17  4991.7 2067.43  4996.9 2066.43  5007.2 2066.24  5007.6 2065.74
  5012.1 2065.74  5012.5 2066.24  5019.9 2068.01    5030 2068.53  5037.5 2067.32
  5042.6 2067.15  5060.2 2070.07  5070.3 2071.19  5110.6 2074.03  5181.1 2075.89
  5221.4 2076.38  5284.4 2078.27    5292 2079.02  5342.4 2080.86  5402.8 2082.17
#Mann= 3 ,-1 , 0
  4484.9     .07       0  5007.2     .05       0  5012.5     .07       0
Bank Sta=5007.2,5012.5
XS Rating Curve= 0 ,0
Exp/Cntr=0.3,0.1

Type RM Length L Ch R = 1 ,14048   ,488,488,488
BEGIN DESCRIPTION:
Rough Creek 30.0
END DESCRIPTION:
XS GIS Cut Line= 3
      1840274.95       13989125.        1840075.       13989125.
      1839525.04     13989424.98
#Sta/Elev= 30
  4792.6 2082.91  4822.6 2080.17  4882.6 2071.13  4932.6 2068.11  4982.6 2066.51
  4990.1 2064.93  5006.3 2064.57  5012.2  2063.8  5012.7  2063.3  5018.4  2063.8
  5022.5 2065.03  5028.1 2064.37  5044.3 2066.12  5082.3 2066.32  5147.8 2068.07
  5191.4 2067.58  5207.6 2065.58  5220.4  2065.4  5229.4 2067.24  5235.1 2067.22
  5243.1 2068.99  5251.2 2069.75  5294.9 2071.46  5354.7 2072.44  5360.4 2073.22
  5436.3 2074.12    5471 2075.75  5523.6 2076.84  5573.5  2079.6    5619 2080.99
#Mann= 3 ,-1 , 0
  4792.6     .07       0  5012.2     .05       0  5018.4     .07       0
Bank Sta=5012.2,5018.4
XS Rating Curve= 0 ,0
Exp/Cntr=0.3,0.1

Type RM Length L Ch R = 1 ,13560   ,473,473,473
BEGIN DESCRIPTION:
Rough Creek 29.0
END DESCRIPTION:
XS GIS Cut Line= 3
      1840174.97       13988675.        1840075.       13988675.
      1839475.03     13989424.97
#Sta/Elev= 30
  4900.5  2080.5  4940.5 2076.57  4950.5 2076.67  4980.5 2073.38  4990.5 2070.33
    4998 2065.71  5007.7 2065.35  5014.1 2061.33  5033.4  2060.4  5033.9  2059.9
  5039.1  2059.9  5039.6  2060.4  5050.9 2060.86  5057.3 2063.01  5064.5 2063.32
  5100.5 2063.67  5142.1 2062.99  5228.6 2064.18    5235 2063.17  5278.2 2064.04
  5284.6  2065.2  5292.6 2065.58  5371.1  2066.2  5435.1 2067.69  5455.9 2067.48
  5526.3 2069.66  5633.6 2070.93  5825.7 2076.81  5947.3 2081.82  5960.9 2081.75
#Mann= 3 ,-1 , 0
  4900.5     .07       0  5033.4     .05       0  5039.6     .07       0
Bank Sta=5033.4,5039.6
XS Rating Curve= 0 ,0
Exp/Cntr=0.3,0.1

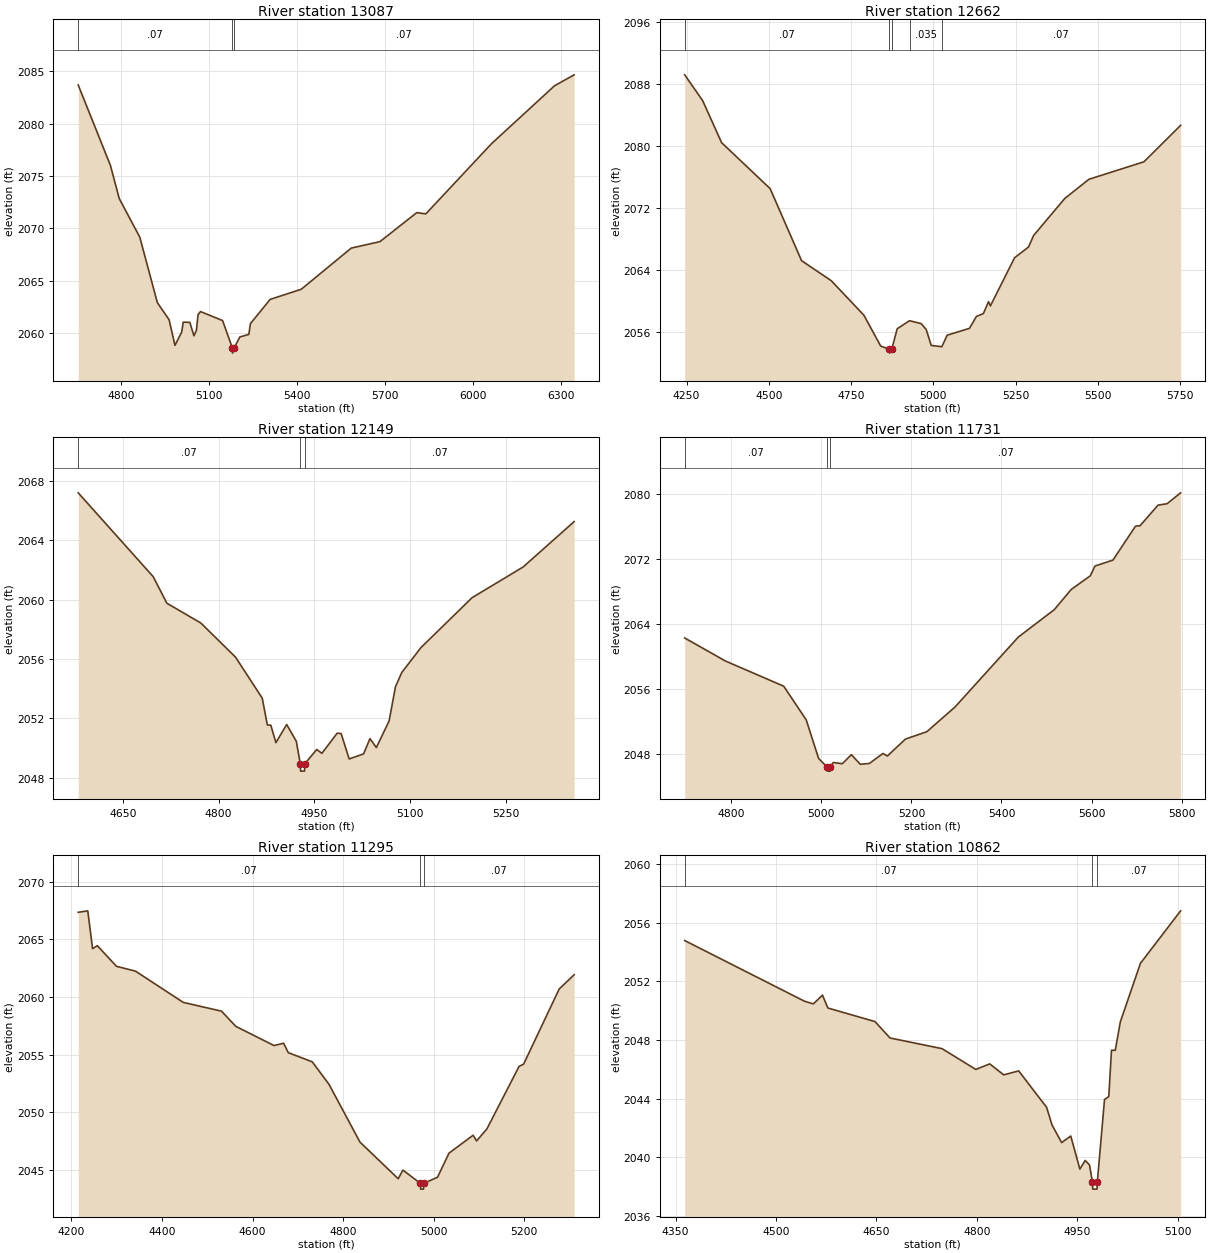
Type RM Length L Ch R = 1 ,13087   ,425,425,425
BEGIN DESCRIPTION:
Rough Creek 28.0
END DESCRIPTION:
XS GIS Cut Line= 3
      1840224.96       13988275.        1839875.       13988275.
        1839275.       13989475.
#Sta/Elev= 30
  4654.8 2083.68  4764.8 2075.99  4794.8 2072.83  4864.8 2069.15  4924.8 2062.89
  4964.8 2061.26  4984.8 2058.81  5007.6 2060.07  5013.1 2061.03  5035.5 2061.01
  5049.5 2059.73  5057.9 2060.23  5063.5 2061.73  5071.8 2062.04  5147.3 2061.18
  5180.5 2058.57    5181 2058.07  5186.8 2058.57    5206 2059.61  5236.8 2059.86
  5242.3 2060.89  5309.4  2063.2  5415.6 2064.17  5586.1  2068.1    5684 2068.72
  5809.7 2071.49  5840.5 2071.37  6064.1 2078.06  6279.3  2083.6  6346.4 2084.65
#Mann= 3 ,-1 , 0
  4654.8     .07       0  5180.5     .05       0  5186.8     .07       0
Bank Sta=5180.5,5186.8
XS Rating Curve= 0 ,0
Exp/Cntr=0.3,0.1

Type RM Length L Ch R = 1 ,12662   ,513,513,513
BEGIN DESCRIPTION:
Mapping XS 960f434e
END DESCRIPTION:
XS GIS Cut Line= 3
      1840329.49     13987892.06      1839677.16     13987937.26
      1838950.01     13988384.37
#Sta/Elev= 30
  4244.4 2089.23    4299  2085.9  4356.7 2080.46  4504.2 2074.52  4599.7 2065.21
    4690 2062.62  4789.2 2058.16  4840.3 2054.17  4866.9 2053.76  4867.4 2053.26
  4873.8 2053.76  4890.4 2056.41  4927.8 2057.45  4963.1 2057.08  4978.5 2056.32
  4993.9 2054.25  5026.1 2054.09  5042.4 2055.58  5109.9 2056.46  5131.2    2058
  5152.5 2058.38  5167.9 2059.91  5173.7 2059.36  5247.2 2065.59  5289.7 2066.98
  5305.1 2068.47  5399.8 2073.25  5473.2 2075.73  5640.4 2077.99  5751.9  2082.7
#Mann= 5 ,-1 , 0
  4244.4     .07       0  4866.9     .05       0  4873.8     .07       0
  4927.8    .035       0  5026.1     .07       0
Bank Sta=4866.9,4873.8
XS Rating Curve= 0 ,0
Exp/Cntr=0.3,0.1

Type RM Length L Ch R = 1 ,12149   ,418,418,418
BEGIN DESCRIPTION:
Rough Creek 27.0
END DESCRIPTION:
XS GIS Cut Line= 3
      1839975.05     13987675.02        1839575.       13987525.
      1839225.05       13987525.
#Sta/Elev= 30
    4580 2067.21  4697.5 2061.56  4718.9 2059.77  4772.3 2058.43  4826.6 2056.13
  4868.4 2053.37  4876.4 2051.56  4881.8 2051.55  4889.8 2050.37  4906.7 2051.59
  4921.8 2050.46    4928 2048.95  4928.5 2048.45  4934.7 2048.45  4935.2 2048.95
  4953.8 2049.91  4961.9 2049.65  4985.9 2051.01  4992.1 2050.98  5004.6 2049.27
  5027.2 2049.61  5037.2 2050.64  5047.2 2050.04  5067.2 2051.83  5077.2 2054.14
  5087.2 2055.11  5117.2 2056.78  5197.2 2060.14  5277.2 2062.21  5357.2 2065.27
#Mann= 3 ,-1 , 0
    4580     .07       0    4928     .05       0  4935.2     .07       0
Bank Sta=4928,4935.2
XS Rating Curve= 0 ,0
Exp/Cntr=0.3,0.1

Type RM Length L Ch R = 1 ,11731   ,436,436,436
BEGIN DESCRIPTION:
Rough Creek 26.0
END DESCRIPTION:
XS GIS Cut Line= 3
      1840025.03       13987175.        1839725.       13987175.
      1838924.99       13987225.
#Sta/Elev= 30
  4696.3 2062.27  4786.3 2059.45  4916.3 2056.34  4966.3  2052.2  4993.8 2047.46
  5012.7  2046.4  5013.2  2045.9  5019.5  2045.9    5020  2046.4  5026.4 2046.96
  5046.4 2046.81  5066.5 2047.92  5086.5 2046.74  5106.5 2046.84  5136.6 2048.07
  5146.6 2047.76  5186.7 2049.84  5234.3 2050.75  5296.9 2053.79  5437.2 2062.37
  5517.3 2065.75  5554.9 2068.23  5597.5 2069.92  5607.5 2071.11  5647.6 2071.84
  5697.7 2076.01  5707.7 2076.06  5747.8  2078.6  5767.8 2078.77  5797.9 2080.11
#Mann= 3 ,-1 , 0
  4696.3     .07       0  5012.7     .05       0    5020     .07       0
Bank Sta=5012.7,5020
XS Rating Curve= 0 ,0
Exp/Cntr=0.3,0.1

Type RM Length L Ch R = 1 ,11295   ,433,433,433
BEGIN DESCRIPTION:
Rough Creek 25.0
END DESCRIPTION:
XS GIS Cut Line= 3
      1840275.03     13987075.01        1839525.       13986825.
      1839225.04     13986874.99
#Sta/Elev= 30
  4215.2 2067.33  4236.3 2067.46  4246.9 2064.18  4257.4 2064.44  4299.6 2062.65
  4341.7 2062.23  4447.1 2059.52  4531.5 2058.76  4563.1 2057.44  4647.4 2055.78
  4668.5 2055.98    4679 2055.16  4731.7 2054.37  4768.6 2052.43  4837.1 2047.41
  4921.5 2044.23    4932 2044.98  4970.5 2043.83    4971 2043.33  4977.3 2043.33
  4977.8 2043.83  5008.3 2044.36  5033.7 2046.45  5086.9    2048  5094.5 2047.51
  5117.3 2048.55  5188.3 2053.97  5198.4 2054.17    5277 2060.69  5309.9 2061.92
#Mann= 3 ,-1 , 0
  4215.2     .07       0  4970.5     .05       0  4977.8     .07       0
Bank Sta=4970.5,4977.8
XS Rating Curve= 0 ,0
Exp/Cntr=0.3,0.1

Type RM Length L Ch R = 1 ,10862   ,441,441,441
BEGIN DESCRIPTION:
Rough Creek 24.0
END DESCRIPTION:
XS GIS Cut Line= 3
      1839924.99       13986825.        1839425.       13986425.
      1839325.01       13986425.
#Sta/Elev= 30
  4363.7  2054.8  4542.2 2050.66  4555.8 2050.47  4569.4 2051.07  4577.4 2050.19
  4647.8 2049.26  4670.2 2048.14  4747.9 2047.41  4798.3 2045.99  4819.1 2046.37
  4839.9 2045.62  4862.3 2045.89    4904  2043.4    4912  2042.2  4926.4 2040.99
    4940 2041.44  4953.6 2039.18  4961.6 2039.77    4968 2039.46  4972.3 2038.31
  4972.8 2037.81  4979.2 2037.81  4979.7 2038.31  4990.4 2043.93  4996.8 2044.14
  5000.8  2047.3  5006.5  2047.3    5014 2049.24    5044 2053.24    5104 2056.83
#Mann= 3 ,-1 , 0
  4363.7     .07       0  4972.3     .05       0  4979.7     .07       0
Bank Sta=4972.3,4979.7
XS Rating Curve= 0 ,0
Exp/Cntr=0.3,0.1

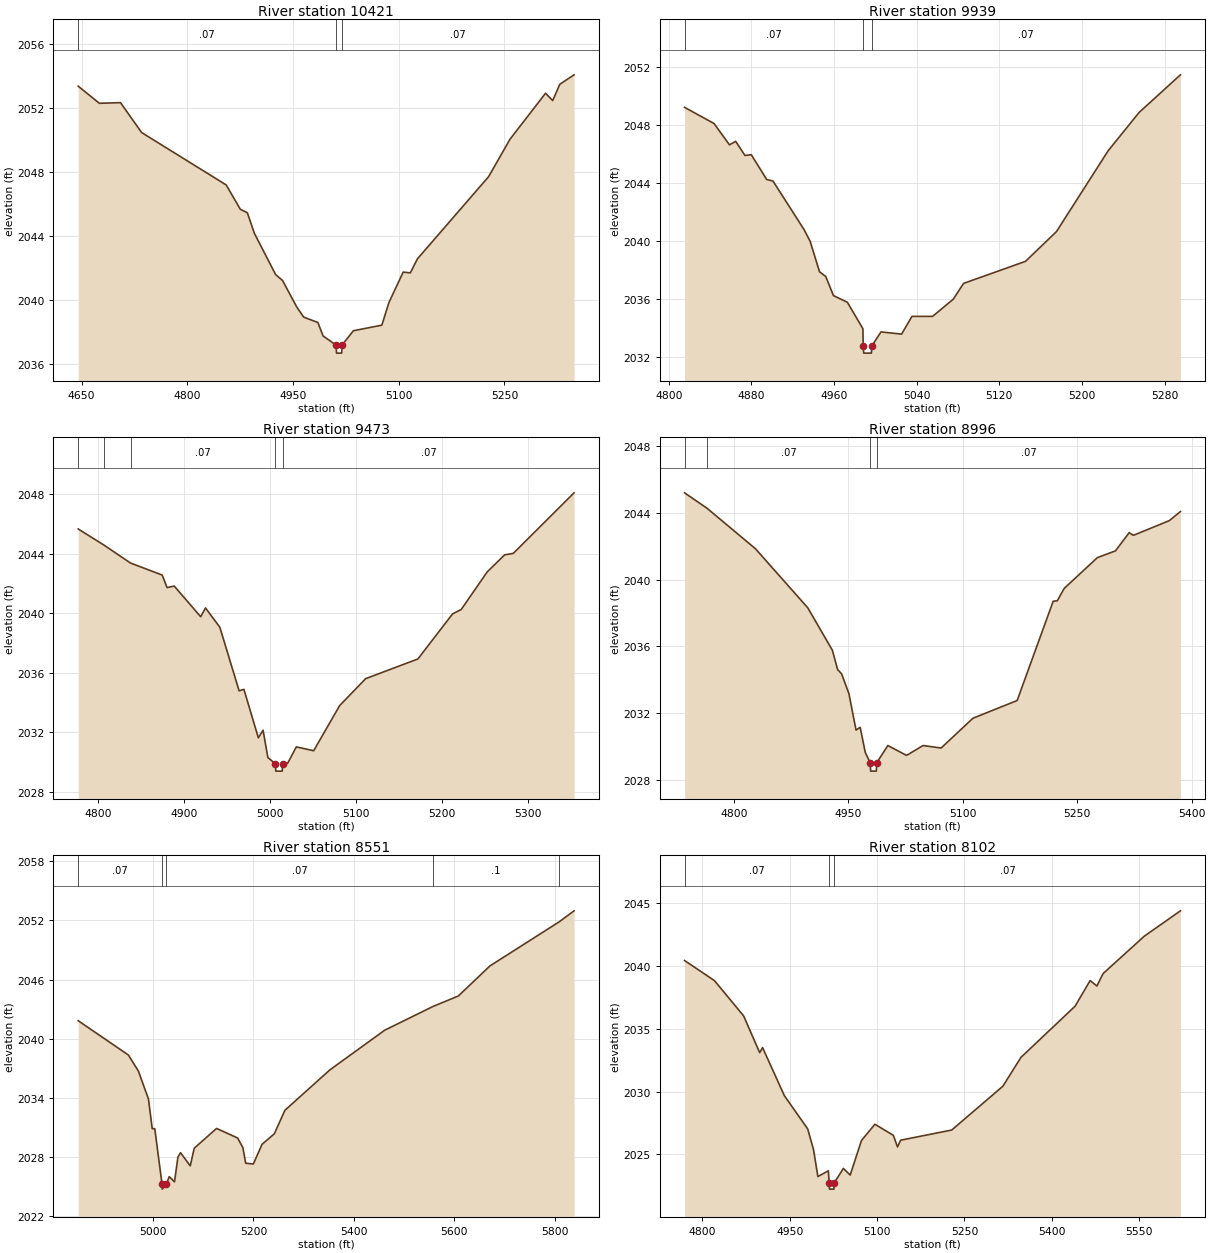
Type RM Length L Ch R = 1 ,10421   ,482,482,482
BEGIN DESCRIPTION:
Rough Creek 23.0
END DESCRIPTION:
XS GIS Cut Line= 3
      1840024.99       13986075.        1839675.       13986075.
      1839325.04     13986025.01
#Sta/Elev= 30
  4645.3 2053.38  4675.3 2052.31  4705.3 2052.35  4735.3 2050.48  4855.3  2047.2
  4875.3 2045.68  4885.3 2045.46  4895.3 2044.17  4925.3  2041.6  4935.3 2041.22
  4955.3 2039.57  4965.3 2038.93  4985.3  2038.6  4992.8 2037.75  5011.3 2037.18
  5011.8 2036.68  5019.1 2036.68  5019.6 2037.18  5035.7 2038.08  5076.1 2038.43
  5086.2 2039.85  5106.4 2041.75  5116.5  2041.7  5126.6 2042.58  5227.6 2047.72
  5257.9 2050.06  5308.4 2052.94  5318.5 2052.48  5328.6  2053.5  5348.8 2054.09
#Mann= 3 ,-1 , 0
  4645.3     .07       0  5011.3     .05       0  5019.6     .07       0
Bank Sta=5011.3,5019.6
XS Rating Curve= 0 ,0
Exp/Cntr=0.3,0.1

Type RM Length L Ch R = 1 ,9939    ,466,466,466
BEGIN DESCRIPTION:
Rough Creek 22.0
END DESCRIPTION:
XS GIS Cut Line= 3
      1839924.96     13985724.97        1839775.       13985625.
      1839475.03       13985625.
#Sta/Elev= 30
  4815.2  2049.2  4843.7 2048.09  4858.7 2046.62  4864.7 2046.86  4873.7 2045.89
  4879.8 2045.94  4894.8 2044.23  4900.8 2044.13  4930.8  2040.8  4936.8 2039.98
  4945.9 2037.88  4951.9 2037.56  4959.4 2036.24  4972.9 2035.78  4987.9 2033.96
  4988.2 2032.78  4988.7 2032.28  4996.1 2032.28  4996.6 2032.78  5005.4 2033.74
  5025.4 2033.59  5035.4 2034.81  5055.4 2034.81  5075.4 2035.99  5085.4 2037.08
  5145.4  2038.6  5175.4 2040.65  5225.4 2046.21  5255.4 2048.85  5295.4 2051.44
#Mann= 3 ,-1 , 0
  4815.2     .07       0  4988.2     .05       0  4996.6     .07       0
Bank Sta=4988.2,4996.6
XS Rating Curve= 0 ,0
Exp/Cntr=0.3,0.1

Type RM Length L Ch R = 1 ,9473    ,477,477,477
BEGIN DESCRIPTION:
Rough Creek 21.0
END DESCRIPTION:
XS GIS Cut Line= 3
      1840025.02     13985275.01        1839825.       13985175.
      1839474.98       13985225.
#Sta/Elev= 30
  4776.4 2045.66  4806.3 2044.58  4837.3 2043.37  4874.2 2042.56  4879.8 2041.72
  4888.2 2041.82    4919 2039.76  4924.6 2040.35  4941.3 2039.05  4963.7 2034.78
  4969.3 2034.88  4986.1 2031.62  4991.6 2032.13  4997.2 2030.29  5005.9 2029.88
  5006.4 2029.38  5013.9 2029.38  5014.4 2029.88  5020.2 2029.91  5030.3 2031.01
  5050.5 2030.75  5080.8 2033.79  5111.1  2035.6  5171.8 2036.92  5212.2 2039.95
  5222.3 2040.25  5252.6 2042.78  5272.8 2043.92  5282.9 2044.02  5353.6 2048.09
#Mann= 5 ,-1 , 0
  4776.4     .07       0  4806.3      .1       0  4837.3     .07       0
  5005.9     .05       0  5014.4     .07       0
Bank Sta=5005.9,5014.4
XS Rating Curve= 0 ,0
Exp/Cntr=0.3,0.1

Type RM Length L Ch R = 1 ,8996    ,445,445,445
BEGIN DESCRIPTION:
Rough Creek 20.0
END DESCRIPTION:
XS GIS Cut Line= 3
      1840074.96     13984824.98        1839825.       13984725.
        1839475.       13984875.
#Sta/Elev= 30
  4735.3 2045.18  4764.7 2044.26  4828.2 2041.84  4896.8 2038.31  4929.1 2035.77
  4935.9 2034.62  4941.2 2034.36  4950.7 2033.19  4960.1    2031  4965.5 2031.17
  4972.2 2029.66  4978.7 2029.05  4979.2 2028.55  4986.7 2028.55  4987.2 2029.05
  5001.8 2030.08  5026.3 2029.49    5048 2030.08  5071.6 2029.93  5113.3 2031.71
  5171.3 2032.77  5218.5  2038.7  5223.9 2038.73    5233 2039.47  5276.5 2041.31
  5300.1 2041.71  5318.2  2042.8  5323.7 2042.64  5370.8 2043.52  5385.3 2044.06
#Mann= 4 ,-1 , 0
  4735.3      .1       0  4764.7     .07       0  4978.7     .05       0
  4987.2     .07       0
Bank Sta=4978.7,4987.2
XS Rating Curve= 0 ,0
Exp/Cntr=0.3,0.1

Type RM Length L Ch R = 1 ,8551    ,449,449,449
BEGIN DESCRIPTION:
Rough Creek 19.0
END DESCRIPTION:
XS GIS Cut Line= 3
      1840024.96       13984325.        1839875.       13984325.
      1839075.02       13984575.
#Sta/Elev= 30
  4850.8 2041.83  4950.8 2038.35  4970.8 2036.71  4990.8 2033.89  4998.3 2030.87
  5003.4 2030.87  5017.9 2025.24  5018.4 2024.74  5026.5 2025.24  5032.2 2026.01
  5042.7 2025.48  5049.5 2027.99  5054.7 2028.44  5074.1  2027.1    5082 2028.89
  5126.5  2030.9  5168.4 2029.93  5178.9 2028.96  5184.6 2027.37  5199.8 2027.29
  5217.1 2029.28  5241.7 2030.36  5262.7 2032.74  5352.3 2036.84  5461.7 2040.87
  5558.5 2043.29  5608.4 2044.34  5671.3 2047.39  5808.6 2051.84  5838.9 2052.98
#Mann= 5 ,-1 , 0
  4850.8     .07       0  5017.9     .05       0  5026.5     .07       0
  5558.5      .1       0  5808.6     .07       0
Bank Sta=5017.9,5026.5
XS Rating Curve= 0 ,0
Exp/Cntr=0.3,0.1

Type RM Length L Ch R = 1 ,8102    ,447,447,447
BEGIN DESCRIPTION:
Rough Creek 18.0
END DESCRIPTION:
XS GIS Cut Line= 3
      1840056.22     13983913.42        1839825.       13983925.
      1839239.62     13984129.86
#Sta/Elev= 30
  4769.3 2040.44  4820.6 2038.84  4870.7 2036.03  4898.3  2033.1  4903.3  2033.5
  4940.7 2029.67  4980.8 2027.02  4990.8 2025.37  4998.3 2023.22  5016.3 2023.68
  5017.7 2022.72  5018.2 2022.22  5025.9 2022.22  5026.4 2022.72  5042.1 2023.87
  5053.8 2023.34  5073.1 2026.09  5096.2 2027.39  5127.9 2026.51  5135.1 2025.58
  5140.4 2026.12  5228.2 2026.93    5316 2030.42  5347.1 2032.72  5440.1  2036.8
  5465.9 2038.84  5477.6 2038.41  5488.2  2039.4    5559 2042.38    5621  2044.4
#Mann= 3 ,-1 , 0
  4769.3     .07       0  5017.7     .05       0  5026.4     .07       0
Bank Sta=5017.7,5026.4
XS Rating Curve= 0 ,0
Exp/Cntr=0.3,0.1

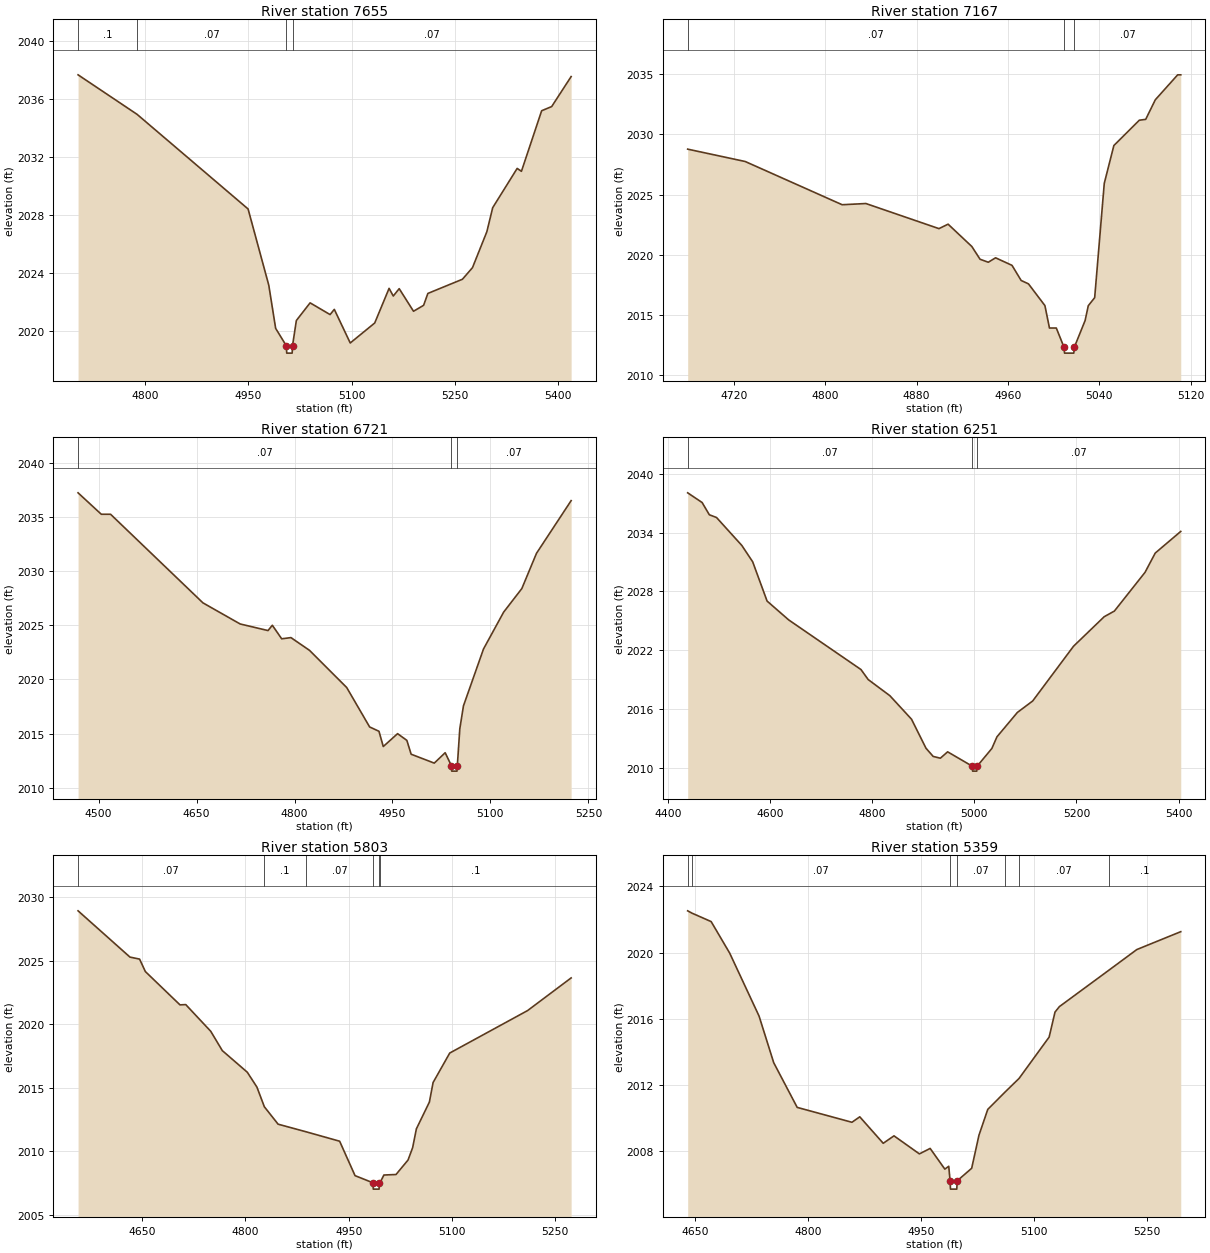
Type RM Length L Ch R = 1 ,7655    ,488,488,488
BEGIN DESCRIPTION:
Rough Creek 17.0
END DESCRIPTION:
XS GIS Cut Line= 3
      1840021.66     13983564.67      1839670.59     13983539.45
      1839374.97     13983324.98
#Sta/Elev= 30
  4702.2 2037.65  4788.1 2034.92  4949.5 2028.39  4979.6 2023.13  4989.6 2020.15
  5005.2 2018.94  5005.7 2018.44  5013.6 2018.44  5014.1 2018.94  5019.7 2020.69
  5039.7 2021.91  5068.8  2021.1  5074.9 2021.46  5098.1 2019.14  5133.7 2020.52
  5154.6 2022.91  5160.7 2022.38  5169.3 2022.89  5190.1 2021.33  5204.8 2021.74
    5211 2022.56  5261.3 2023.54  5275.9 2024.34  5296.8 2026.82  5305.3 2028.48
  5340.9 2031.19  5347.1 2030.99  5376.5 2035.17  5391.1 2035.46  5419.4 2037.53
#Mann= 4 ,-1 , 0
  4702.2      .1       0  4788.1     .07       0  5005.2     .05       0
  5014.1     .07       0
Bank Sta=5005.2,5014.1
XS Rating Curve= 0 ,0
Exp/Cntr=0.3,0.1

Type RM Length L Ch R = 1 ,7167    ,446,446,446
BEGIN DESCRIPTION:
Rough Creek 16.0
END DESCRIPTION:
XS GIS Cut Line= 3
      1839874.99     13983324.99        1839625.       13983125.
      1839525.04     13983075.02
#Sta/Elev= 30
  4679.5 2028.78  4729.9 2027.75  4814.8 2024.15  4835.6 2024.25  4899.6 2022.16
  4907.6 2022.53  4928.4 2020.67  4935.6 2019.61  4942.8 2019.36  4949.2 2019.73
  4963.6  2019.1  4971.6 2017.84    4978 2017.56  4992.4 2015.75  4996.4 2013.88
  5002.4 2013.88  5009.1 2012.29  5009.6 2011.79  5017.7 2011.79  5018.2 2012.29
  5027.6  2014.5  5030.4 2015.74    5036 2016.41  5044.4 2025.93  5052.8 2029.08
  5075.1 2031.19  5080.7 2031.26  5089.1 2032.89  5108.7 2034.97  5111.4 2034.97
#Mann= 3 ,-1 , 0
  4679.5     .07       0  5009.1     .05       0  5018.2     .07       0
Bank Sta=5009.1,5018.2
XS Rating Curve= 0 ,0
Exp/Cntr=0.3,0.1

Type RM Length L Ch R = 1 ,6721    ,470,470,470
BEGIN DESCRIPTION:
Rough Creek 15.0
END DESCRIPTION:
XS GIS Cut Line= 3
      1840274.99     13983124.99        1839875.       13982775.
        1839675.       13982675.
#Sta/Elev= 30
  4468.5 2037.23  4504.1 2035.25  4518.3 2035.25  4659.7 2027.07  4716.7 2025.12
  4759.4 2024.51    4766    2025  4780.3 2023.75  4794.5 2023.86    4823 2022.68
  4879.9 2019.25    4915 2015.61  4929.3 2015.21  4935.9  2013.8  4957.8 2014.99
    4972 2014.37  4978.6 2013.09    5014 2012.27  5030.7 2013.23  5040.2 2012.03
  5040.7 2011.53  5048.8 2011.53  5049.3 2012.03  5053.1 2015.44  5058.7 2017.56
  5089.4 2022.81  5120.2 2026.21  5148.1 2028.39  5170.5 2031.64  5223.6 2036.51
#Mann= 3 ,-1 , 0
  4468.5     .07       0  5040.2     .05       0  5049.3     .07       0
Bank Sta=5040.2,5049.3
XS Rating Curve= 0 ,0
Exp/Cntr=0.3,0.1

Type RM Length L Ch R = 1 ,6251    ,448,448,448
BEGIN DESCRIPTION:
Rough Creek 14.0
END DESCRIPTION:
XS GIS Cut Line= 3
      1840574.98     13982824.98        1840175.       13982425.
      1839774.96       13982425.
#Sta/Elev= 30
  4438.7 2038.05    4467 2037.06  4481.1 2035.81  4495.2 2035.53  4544.7 2032.68
    4566 2031.01  4594.2    2027  4636.7 2025.07  4778.1 2020.01  4792.2 2018.99
  4834.7 2017.34  4877.1 2014.94  4905.4 2011.98  4919.5 2011.14  4933.6 2010.96
  4947.8 2011.61  4996.2 2010.14  4996.7 2009.64    5005 2009.64  5005.5 2010.14
  5034.4 2011.95  5044.4 2013.14  5084.4 2015.63  5114.4  2016.8  5194.4 2022.39
  5254.4  2025.4  5274.4 2025.98  5334.4 2029.93  5354.4  2031.9  5404.4 2034.11
#Mann= 3 ,-1 , 0
  4438.7     .07       0  4996.2     .05       0  5005.5     .07       0
Bank Sta=4996.2,5005.5
XS Rating Curve= 0 ,0
Exp/Cntr=0.3,0.1

Type RM Length L Ch R = 1 ,5803    ,444,444,444
BEGIN DESCRIPTION:
Rough Creek 13.0
END DESCRIPTION:
XS GIS Cut Line= 3
      1840724.99     13982574.98        1840525.       13982175.
      1840274.95     13982074.98
#Sta/Elev= 30
  4556.8 2028.92  4632.2 2025.28  4646.2 2025.12  4654.6 2024.14  4704.9 2021.52
  4713.3 2021.54  4749.6 2019.44  4766.4 2017.92  4802.7 2016.22  4816.7 2015.05
  4827.5  2013.5  4847.5 2012.13  4887.6 2011.54  4936.9 2010.79  4959.3 2008.08
  4985.3 2007.52  4985.8 2007.02  4994.2 2007.02  4994.7 2007.52  4995.9 2007.56
  5001.2 2008.13  5018.8 2008.17  5036.3 2009.31    5043 2010.29  5048.4 2011.76
  5067.3 2013.87  5072.7 2015.41  5096.9 2017.73    5210 2021.07  5273.3 2023.64
#Mann= 6 ,-1 , 0
  4556.8     .07       0  4827.5      .1       0  4887.6     .07       0
  4985.3     .05       0  4994.7     .07       0  4995.9      .1       0
Bank Sta=4985.3,4994.7
XS Rating Curve= 0 ,0
Exp/Cntr=0.3,0.1

Type RM Length L Ch R = 1 ,5359    ,379,379,379
BEGIN DESCRIPTION:
Rough Creek 12.0
END DESCRIPTION:
XS GIS Cut Line= 3
        1840975.       13982325.        1840875.       13981975.
      1840724.97     13981724.96
#Sta/Elev= 30
  4639.9 2022.52  4645.6 2022.38  4671.1 2021.87  4695.8 2019.96  4734.8 2016.16
  4754.3 2013.34  4785.5 2010.64  4858.3 2009.74  4868.7 2010.07  4899.9 2008.47
  4914.2 2008.92    4948 2007.83  4962.3 2008.16  4981.8 2006.91    4987 2007.08
  4988.8  2006.2  4989.3  2005.7  4997.7  2005.7  4998.2  2006.2  5017.5 2006.96
  5027.2 2008.96  5038.9 2010.52  5062.4 2011.59  5080.5 2012.39  5120.5 2014.89
  5128.3  2016.4  5134.1 2016.73  5199.6 2018.92  5237.1 2020.18  5295.5 2021.26
#Mann= 7 ,-1 , 0
  4639.9    .035       0  4645.6     .07       0  4988.8     .05       0
  4998.2     .07       0  5062.4      .1       0  5080.5     .07       0
  5199.6      .1       0
Bank Sta=4988.8,4998.2
XS Rating Curve= 0 ,0
Exp/Cntr=0.3,0.1