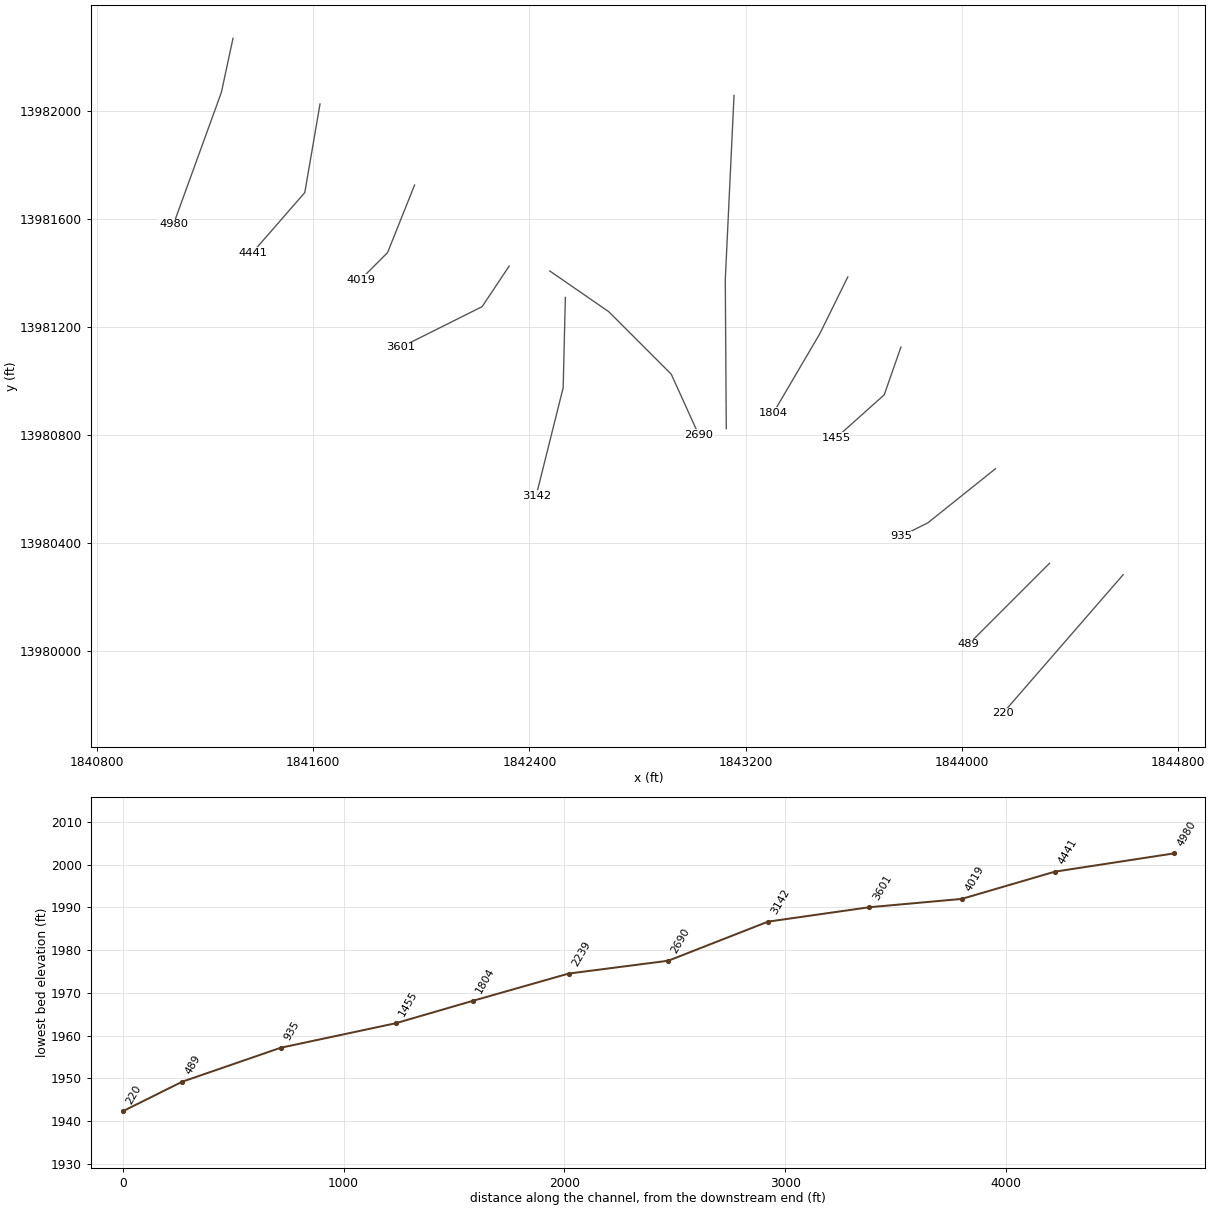
HEC-RAS study Rough Creek.prj: Rough Creek Base Level Engineering

--- Rough Creek.g01 (geometry) --- (continued)

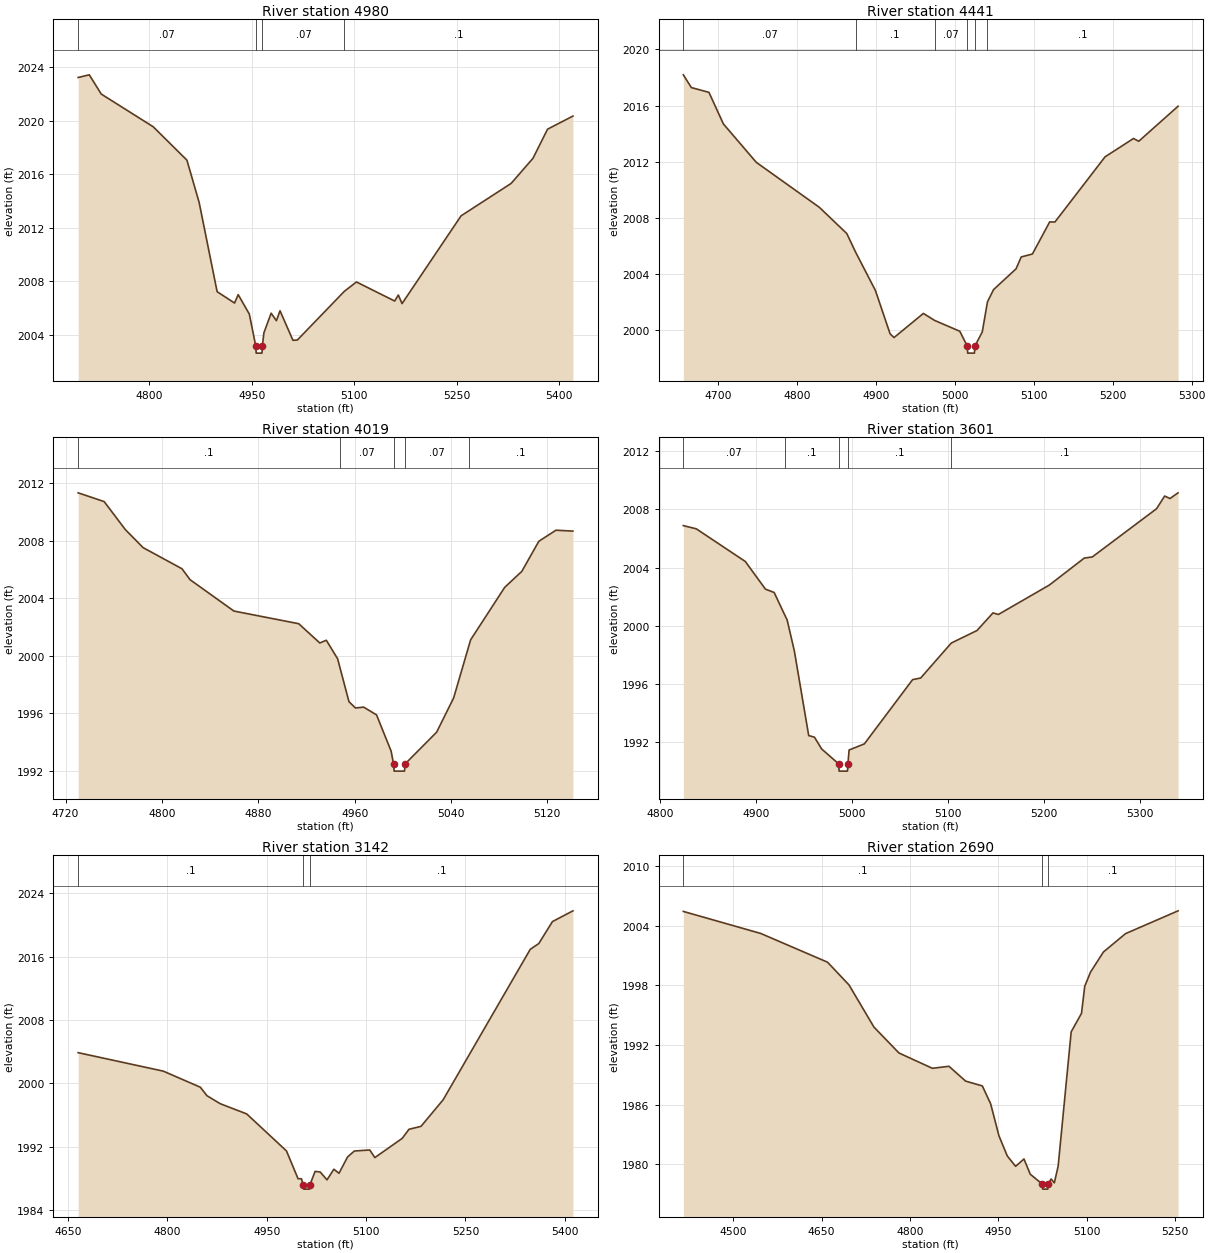
Type RM Length L Ch R = 1 ,4980    ,539,539,539
BEGIN DESCRIPTION:
Rough Creek 11.0
END DESCRIPTION:
XS GIS Cut Line= 3
      1841302.96     13982268.07      1841259.76      13982067.5
      1841082.76     13981580.11
#Sta/Elev= 30
  4696.1 2023.25  4712.4 2023.45  4729.9 2022.01  4805.9 2019.56  4855.2 2017.06
  4873.1 2013.89  4899.4 2007.21  4924.9 2006.36  4930.2 2006.99  4946.5 2005.53
    4956 2003.11  4956.5 2002.61    4965 2002.61  4965.5 2003.11  4967.8 2004.13
  4978.4  2005.6  4986.1 2005.04  4991.4 2005.78  5010.3 2003.57  5016.7 2003.59
  5085.5 2007.24  5103.2 2007.94  5159.1 2006.51  5164.4 2006.96  5169.9 2006.32
  5256.2 2012.89  5329.5 2015.32  5361.4  2017.2  5382.7 2019.38  5419.8 2020.36
#Mann= 4 ,-1 , 0
  4696.1     .07       0    4956     .05       0  4965.5     .07       0
  5085.5      .1       0
Bank Sta=4956,4965.5
XS Rating Curve= 0 ,0
Exp/Cntr=0.3,0.1

Type RM Length L Ch R = 1 ,4441    ,422,422,422
BEGIN DESCRIPTION:
Rough Creek 10.0
END DESCRIPTION:
XS GIS Cut Line= 3
      1841625.01     13982025.03      1841568.61     13981697.11
      1841374.99     13981474.99
#Sta/Elev= 30
  4655.4 2018.19  4665.6 2017.28  4687.9 2016.94  4706.2 2014.69  4747.9 2011.95
  4827.9 2008.74  4862.7 2006.87  4873.9 2005.54    4899 2002.81  4917.6 1999.72
  4922.6 1999.45  4959.8 2001.17  4974.2 2000.67    5006  1999.9  5015.5 1998.84
    5016 1998.34  5024.6 1998.34  5025.1 1998.84  5034.5 1999.85  5041.1    2002
  5048.8 2002.87  5077.3 2004.35  5083.9  2005.2  5098.1 2005.41    5120  2007.7
  5126.6 2007.69  5190.2 2012.34  5226.3 2013.65  5232.9 2013.45  5282.8 2015.95
#Mann= 6 ,-1 , 0
  4655.4     .07       0  4873.9      .1       0  4974.2     .07       0
  5015.5     .05       0  5025.1     .07       0  5041.1      .1       0
Bank Sta=5015.5,5025.1
XS Rating Curve= 0 ,0
Exp/Cntr=0.3,0.1

Type RM Length L Ch R = 1 ,4019    ,418,418,418
BEGIN DESCRIPTION:
Rough Creek 9.0
END DESCRIPTION:
XS GIS Cut Line= 3
        1841975.     13981725.01        1841875.       13981475.
        1841775.       13981375.
#Sta/Elev= 30
  4730.5 2011.32  4752.1 2010.71  4769.6 2008.77  4784.4 2007.51  4816.7 2006.04
  4823.4 2005.28  4859.8  2003.1  4913.6 2002.22  4931.1 2000.88  4936.5 2001.07
  4945.9 1999.78  4947.5 1999.27  4955.3  1996.8  4960.7 1996.36  4967.5 1996.42
  4978.2 1995.88  4990.3 1993.36  4992.3 1992.47  4992.8 1991.97  5001.4 1991.97
  5001.9 1992.47  5028.1 1994.68  5042.2 1997.06  5054.8 2000.67  5056.3  2001.1
  5084.6 2004.75  5098.8 2005.86  5112.9 2007.95  5127.1 2008.72  5141.2 2008.66
#Mann= 5 ,-1 , 0
  4730.5      .1       0  4947.5     .07       0  4992.3     .05       0
  5001.9     .07       0  5054.8      .1       0
Bank Sta=4992.3,5001.9
XS Rating Curve= 0 ,0
Exp/Cntr=0.3,0.1

Type RM Length L Ch R = 1 ,3601    ,459,459,459
BEGIN DESCRIPTION:
Rough Creek 8.0
END DESCRIPTION:
XS GIS Cut Line= 3
      1842325.01     13981425.01        1842225.       13981275.
        1841925.       13981125.
#Sta/Elev= 30
  4824.4 2006.88  4837.9 2006.66    4889 2004.42    4910 2002.52  4919.1 2002.29
  4930.3 2000.72  4932.6 2000.41  4940.1 1998.29  4955.1 1992.47  4961.1 1992.36
  4968.6 1991.55  4986.3 1990.53  4986.8 1990.03  4995.5 1990.03    4996 1990.53
  4997.2 1991.48  5013.1  1991.9  5063.4 1996.31  5071.8 1996.42  5103.7 1998.82
  5130.5 1999.68  5147.2 2000.89  5152.8 2000.78  5205.9  2002.8  5242.3 2004.65
  5250.7 2004.73  5317.7 2008.04  5326.1 2008.91  5331.7 2008.74  5340.1 2009.13
#Mann= 5 ,-1 , 0
  4824.4     .07       0  4930.3      .1       0  4986.3     .05       0
    4996      .1       0  5103.7      .1       0
Bank Sta=4986.3,4996
XS Rating Curve= 0 ,0
Exp/Cntr=0.3,0.1

Type RM Length L Ch R = 1 ,3142    ,452,452,452
BEGIN DESCRIPTION:
Rough Creek 7.0
END DESCRIPTION:
XS GIS Cut Line= 3
      1842533.08     13981309.31        1842525.       13980975.
        1842425.     13980575.01
#Sta/Elev= 30
  4665.5 2003.88    4794 2001.55  4849.9 1999.52  4859.9 1998.45  4879.9 1997.44
  4919.9 1996.15  4979.9 1991.48  4997.4 1987.97  5002.5 1987.97  5005.4 1987.16
  5005.9 1986.66  5014.6 1986.66  5015.1 1987.16  5023.1  1988.9  5030.8 1988.82
  5041.1 1987.83  5051.4 1989.17  5059.2 1988.66  5072.1 1990.72  5082.4 1991.47
  5105.6  1991.6  5113.3 1990.64  5154.5 1993.06  5164.8 1994.21  5182.9 1994.58
  5216.4 1997.94  5347.8 2016.92  5360.7 2017.65  5381.3 2020.42  5412.2 2021.78
#Mann= 3 ,-1 , 0
  4665.5      .1       0  5005.4     .05       0  5015.1      .1       0
Bank Sta=5005.4,5015.1
XS Rating Curve= 0 ,0
Exp/Cntr=0.3,0.1

Type RM Length L Ch R = 1 ,2690    ,451,451,451
BEGIN DESCRIPTION:
Rough Creek 6.0
END DESCRIPTION:
XS GIS Cut Line= 4
      1842475.53     13981406.89      1842693.58     13981256.42
        1842925.       13981025.       1843027.2      13980799.7
#Sta/Elev= 30
  4415.3 2005.42  4546.5 2003.21    4660 2000.32  4696.4 1998.04  4738.8  1993.8
  4781.2  1991.2  4837.8 1989.66  4866.1 1989.86  4894.4 1988.37  4922.7 1987.89
  4936.8  1986.1  4950.9 1982.88  4965.1 1980.85  4979.2 1979.81  4993.4 1980.55
    5004 1979.02  5024.6 1978.02  5025.1 1977.52  5033.9 1977.52  5034.4 1978.02
  5039.4 1978.54  5044.9 1978.15  5051.4 1979.83  5073.5 1993.32    5091 1995.18
  5096.5  1997.9  5106.3 1999.32  5128.3 2001.35  5165.8 2003.19  5254.9 2005.48
#Mann= 3 ,-1 , 0
  4415.3      .1       0  5024.6     .05       0  5034.4      .1       0
Bank Sta=5024.6,5034.4
XS Rating Curve= 0 ,0
Exp/Cntr=0.3,0.1

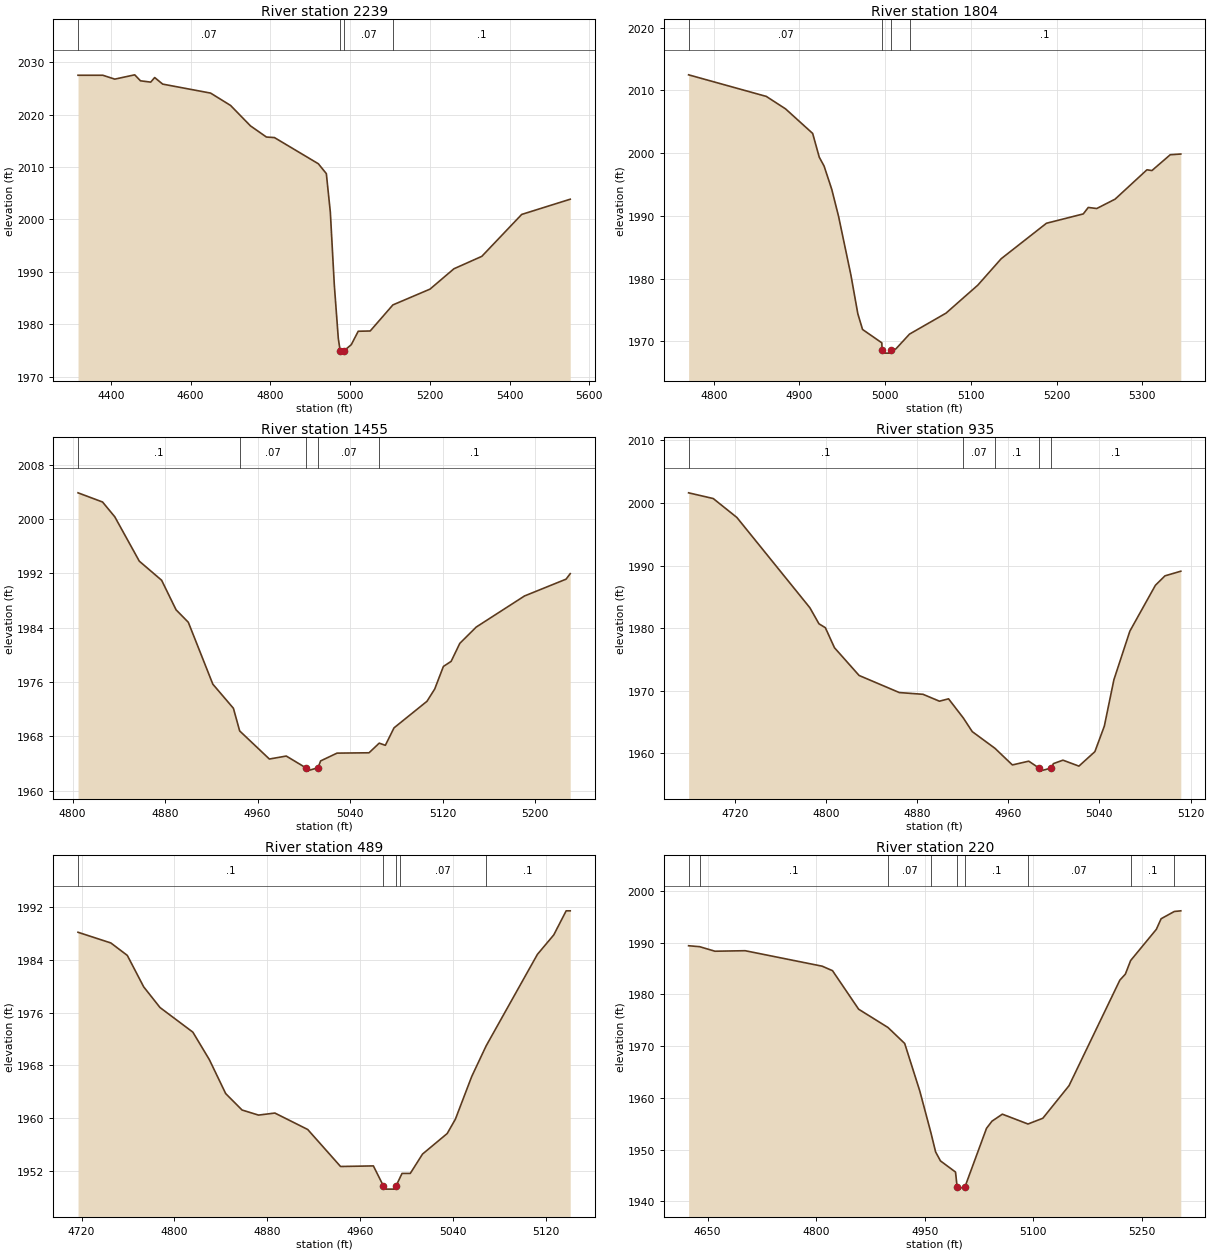
Type RM Length L Ch R = 1 ,2239    ,435,435,435
BEGIN DESCRIPTION:
Rough Creek 5.0
END DESCRIPTION:
XS GIS Cut Line= 3
      1843157.41     13982057.05        1843125.       13981375.
      1843128.67     13980823.33
#Sta/Elev= 30
  4317.7 2027.49  4379.8 2027.49  4409.9 2026.75  4459.9 2027.57  4474.3 2026.43
    4500 2026.18    4510 2027.05    4530  2025.8  4650.1 2024.09  4700.2 2021.74
  4750.2 2017.84  4790.3 2015.71  4810.3 2015.61  4920.4 2010.62  4940.5 2008.74
  4950.5 2001.41  4960.5 1987.51  4970.5 1977.32  4975.1 1975.02  4975.6 1974.52
  4985.8 1975.02    5003 1976.13  5020.5 1978.69  5050.5 1978.74  5107.4 1983.71
  5200.5 1986.72  5260.5  1990.6  5330.5 1992.97  5430.5 2000.96  5552.2 2003.86
#Mann= 4 ,-1 , 0
  4317.7     .07       0  4975.1     .05       0  4985.8     .07       0
  5107.4      .1       0
Bank Sta=4975.1,4985.8
XS Rating Curve= 0 ,0
Exp/Cntr=0.3,0.1

Type RM Length L Ch R = 1 ,1804    ,349,349,349
BEGIN DESCRIPTION:
Rough Creek 4.0
END DESCRIPTION:
XS GIS Cut Line= 3
      1843578.39     13981384.86        1843475.       13981175.
      1843302.64      13980881.4
#Sta/Elev= 30
  4770.6 2012.47  4861.3 2009.03  4883.8 2007.04  4915.4 2003.13  4923.1 1999.34
  4928.7 1997.94  4937.7 1994.21  4945.6 1989.93    4960 1980.58  4968.1  1974.4
  4973.6  1971.9  4996.1 1969.77  4996.4 1968.63  4996.9 1968.13  5006.6 1968.13
  5007.1 1968.63  5012.4 1968.79  5028.4 1971.16    5071  1974.5  5108.1 1978.96
  5135.4 1983.17  5188.2 1988.82  5231.2 1990.31    5237 1991.34  5246.9 1991.17
  5268.3 1992.66  5305.5 1997.34  5311.3 1997.22  5332.7 1999.74    5345 1999.85
#Mann= 4 ,-1 , 0
  4770.6     .07       0  4996.4     .05       0  5007.1     .07       0
  5028.4      .1       0
Bank Sta=4996.4,5007.1
XS Rating Curve= 0 ,0
Exp/Cntr=0.3,0.1

Type RM Length L Ch R = 1 ,1455    ,520,520,520
BEGIN DESCRIPTION:
Rough Creek 3.0
END DESCRIPTION:
XS GIS Cut Line= 3
      1843775.01     13981125.03      1843713.32     13980948.57
      1843535.24     13980789.51
#Sta/Elev= 30
  4804.7 2003.87  4825.9 2002.52  4836.5 2000.34  4857.7 1993.81    4877    1991
  4889.5 1986.65  4900.1 1984.81  4921.3  1975.7  4939.1 1972.15  4944.5 1968.82
  4970.2 1964.68  4984.8 1965.12  5001.6  1963.4  5002.1  1962.9  5012.3  1963.4
  5014.5  1964.4  5028.7 1965.55  5056.4  1965.6  5065.2 1967.02  5070.5  1966.7
    5078 1969.27  5106.5 1973.18  5113.2 1974.99  5120.7 1978.31  5127.4 1979.06
  5134.9 1981.71  5149.1 1984.11  5190.9 1988.69  5226.8 1991.16  5230.4 1991.97
#Mann= 5 ,-1 , 0
  4804.7      .1       0  4944.5     .07       0  5001.6     .05       0
  5012.3     .07       0  5065.2      .1       0
Bank Sta=5001.6,5012.3
XS Rating Curve= 0 ,0
Exp/Cntr=0.3,0.1

Type RM Length L Ch R = 1 ,935     ,446,446,446
BEGIN DESCRIPTION:
Rough Creek 2.0
END DESCRIPTION:
XS GIS Cut Line= 3
      1844124.98     13980674.98        1843875.       13980475.
      1843775.03     13980425.01
#Sta/Elev= 30
  4679.5 2001.63  4701.1 2000.72  4721.9 1997.69  4785.9 1983.28  4793.9 1980.71
  4799.5 1980.09  4807.5 1976.89  4829.1 1972.46  4864.4 1969.73  4885.2 1969.45
  4899.6 1968.35  4907.6 1968.73  4920.6 1965.66  4928.4 1963.49  4948.3 1960.83
  4963.6 1958.17    4978 1958.77  4986.9 1957.68  4987.4 1957.18  4997.9 1957.68
  4999.6 1958.38    5008 1958.93    5022 1957.98    5036 1960.29  5044.3 1964.37
  5052.7 1971.78  5066.7 1979.54  5089.1 1986.86  5097.5 1988.37  5111.4 1989.11
#Mann= 5 ,-1 , 0
  4679.5      .1       0  4920.6     .07       0  4948.3      .1       0
  4986.9     .05       0  4997.9      .1       0
Bank Sta=4986.9,4997.9
XS Rating Curve= 0 ,0
Exp/Cntr=0.3,0.1

Type RM Length L Ch R = 1 ,489     ,269,269,269
BEGIN DESCRIPTION:
Rough Creek 1.0
END DESCRIPTION:
XS GIS Cut Line= 3
      1844325.02     13980325.02        1844125.       13980125.
      1844024.99     13980024.99
#Sta/Elev= 30
  4716.9 1988.17  4745.2 1986.55  4759.4 1984.66  4773.5  1979.9  4787.6 1976.76
  4815.9 1973.03  4830.1 1968.87  4844.2 1963.72  4858.3 1961.23  4872.5 1960.46
  4886.6 1960.77  4914.9 1958.28  4943.2 1952.67  4971.5 1952.76  4980.1 1949.74
  4980.6 1949.24  4990.6 1949.24  4991.1 1949.74  4994.6 1951.03  4996.2 1951.62
  5003.3 1951.62  5013.9 1954.56  5035.1 1957.66  5042.2 1959.84  5056.3 1966.32
  5068.7 1970.95  5112.9 1984.82    5127 1987.77  5137.7 1991.42  5141.2 1991.42
#Mann= 5 ,-1 , 0
  4716.9      .1       0  4980.1     .05       0  4991.1      .1       0
  4994.6     .07       0  5068.7      .1       0
Bank Sta=4980.1,4991.1
XS Rating Curve= 0 ,0
Exp/Cntr=0.3,0.1

Type RM Length L Ch R = 1 ,220     ,0,0,0
BEGIN DESCRIPTION:
Rough Creek 0.0
END DESCRIPTION:
XS GIS Cut Line= 2
      1844597.77       13980283.      1844152.07     13979769.57
#Sta/Elev= 30
  4623.8 1989.39    4639 1989.21  4660.2 1988.33  4701.9 1988.43  4808.3 1985.44
  4822.6 1984.57  4858.7 1977.12  4899.2 1973.59  4922.3  1970.5  4943.2 1961.29
  4958.6  1953.2    4965 1949.54  4971.7  1947.8  4992.5 1945.64  4994.7 1942.84
  4995.2 1942.34  5005.7 1942.84  5035.3 1954.09  5042.9 1955.48  5057.2 1956.83
  5092.6 1954.93  5113.1 1956.04  5149.3 1962.34  5219.5 1982.74  5227.1  1983.9
  5234.4 1986.53  5269.9 1992.56  5276.5 1994.61  5294.7 1996.01  5303.7 1996.14
#Mann= 9 ,-1 , 0
  4623.8     .07       0    4639      .1       0  4899.2     .07       0
  4958.6      .1       0  4994.7     .05       0  5005.7      .1       0
  5092.6     .07       0  5234.4      .1       0  5294.7     .07       0
Bank Sta=4994.7,5005.7
XS Rating Curve= 0 ,0
Exp/Cntr=0.3,0.1

Chan Stop Cuts=-1
Use User Specified Reach Order=0
Composite Channel Slope=5