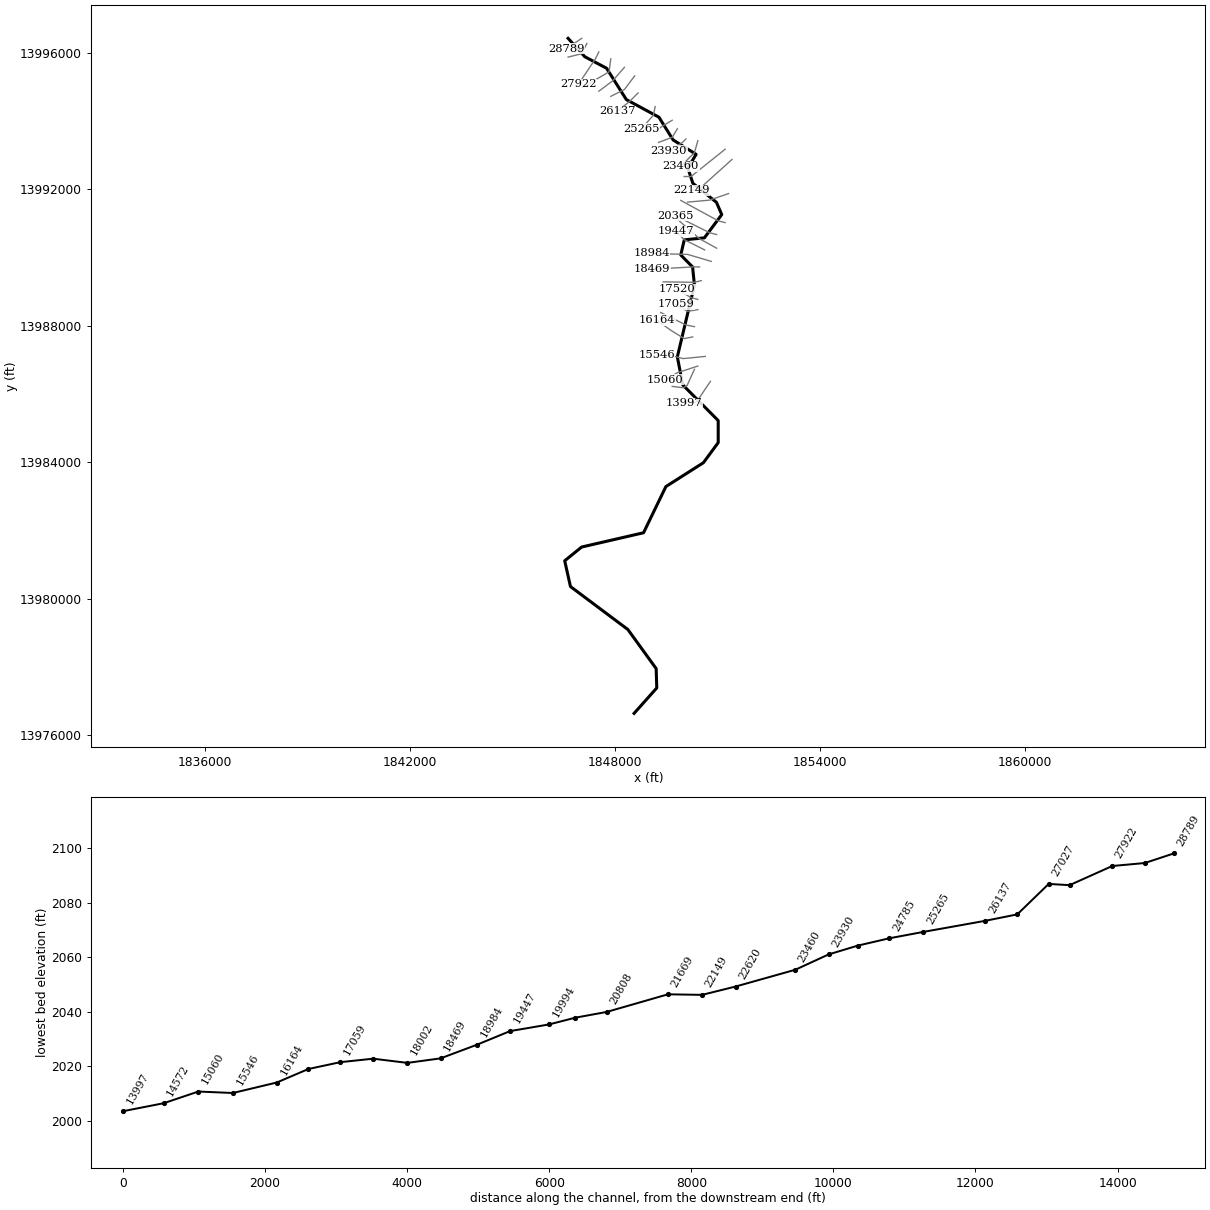
--- Rough Hollow.prj (project) ---

Proj Title=Rough Hollow Base Level Engineering
Current Plan=p01
Default Exp/Contr=0.3,0.1
English Units
Geom File=g01
Flow File=f01
Plan File=p01
Y Axis Title=Elevation
X Axis Title(PF)=Main Channel Distance
X Axis Title(XS)=Station
BEGIN DESCRIPTION:
Rough Hollow
END DESCRIPTION:
DSS Export Rating Curves= 0
DSS Export Rating Curve Sorted= 0
DSS Export Volume Flow Curves= 0
DXF OffsetX= 0
DXF OffsetY= 0
DXF ScaleX= 1
DXF ScaleY= 10

--- Rough Hollow.p01 (plan) ---

Plan Title=Multiple Run
Short Identifier=Multiple
Geom File=g01
Flow File=f01
Subcritical Flow
K Sum by GR= 0
Std Step Tol= 0.01
Critical Tol= 0.01
Num of Std Step Trials= 20
Max Error Tol= 0.3
Flow Tol Ratio= 0.001
Split Flow NTrial= 30
Split Flow Tol= 0.02
Split Flow Ratio= 0.02
Log Output Level= 0
Friction Slope Method= 1
Unsteady Friction Slope Method= 2
Unsteady Bridges Friction Slope Method= 1
Parabolic Critical Depth
Global Vel Dist=  1 , 1 , 1
Global Log Level= 0
CheckData=True
Encroach Param= -1, 0, 0, 0
BEGIN DESCRIPTION:
Multiple Run
END DESCRIPTION:

--- Rough Hollow.f01 (steady flow) ---

Flow Title=Multiple
Number of Profiles=7
Profile Names=10-year,25-year,50-year,1pct_min,100-year,1pct_plu,500-year
River Rch & RM= Rough Hollow,Reach-1,28789
    2099    3695    5256    3601    7185   14337   13290
River Rch & RM= Rough Hollow,Reach-1,22620
    4754    8625   12513    8720   17398   34714   33298
River Rch & RM= Rough Hollow,Reach-1,15546
    5778   10550   15375   10755   21459   42817   41385
River Rch & RM= Rough Hollow,Reach-1,12315
    5999   10972   16008   11210   22366   44626   43225
River Rch & RM= Rough Hollow,Reach-1,7331
    6095   11148   16264   11388   22723   45338   43909
River Rch & RM= Rough Hollow,Reach-1,6224
    6283   11501   16789   11761   23467   46823   45388
River Rch & RM= Rough Hollow,Reach-1,4672
    6488   11898   17389   12196   24335   48554   47177
Boundary for River Rch & Prof#=Rough Hollow,Reach-1,1
Up Type=0
Dn Type=3
Dn Slope=0.005
Boundary for River Rch & Prof#=Rough Hollow,Reach-1,2
Up Type=0
Dn Type=3
Dn Slope=0.005
Boundary for River Rch & Prof#=Rough Hollow,Reach-1,3
Up Type=0
Dn Type=3
Dn Slope=0.005
Boundary for River Rch & Prof#=Rough Hollow,Reach-1,4
Up Type=0
Dn Type=3
Dn Slope=0.005
Boundary for River Rch & Prof#=Rough Hollow,Reach-1,5
Up Type=0
Dn Type=3
Dn Slope=0.005
Boundary for River Rch & Prof#=Rough Hollow,Reach-1,6
Up Type=0
Dn Type=3
Dn Slope=0.005
Boundary for River Rch & Prof#=Rough Hollow,Reach-1,7
Up Type=0
Dn Type=3
Dn Slope=0.005

--- Rough Hollow.g01 (geometry) ---

Geom Title=Existing Conditions
Program Version=4.10

River Reach=Rough Hollow    ,Reach-1
Reach XY= 30
        1846625.       13996425.      1847115.18     13995885.47
      1847752.48     13995548.33      1848330.26     13994630.47
       1849284.8     13994114.52      1849701.27      13993447.3
        1850375.       13993025.      1850132.32      13992625.1
      1850278.83     13992176.58      1850969.56     13991619.81
      1851124.97     13991259.58      1850616.65     13990578.19
      1850027.05     13990519.16        1849925.       13990075.
      1850271.46     13989723.54      1850324.93     13989195.03
      1849824.51      13987090.2      1849983.14     13986268.94
      1851021.46     13985223.54      1851021.39      13984576.5
      1850588.21     13983988.63      1849488.61     13983288.24
      1848834.98     13981935.69      1847021.77     13981516.75
       1846526.2      13981114.5      1846694.58     13980358.93
      1848376.26     13979099.58      1849204.18     13977954.44
      1849222.21     13977387.49      1848557.74     13976642.26

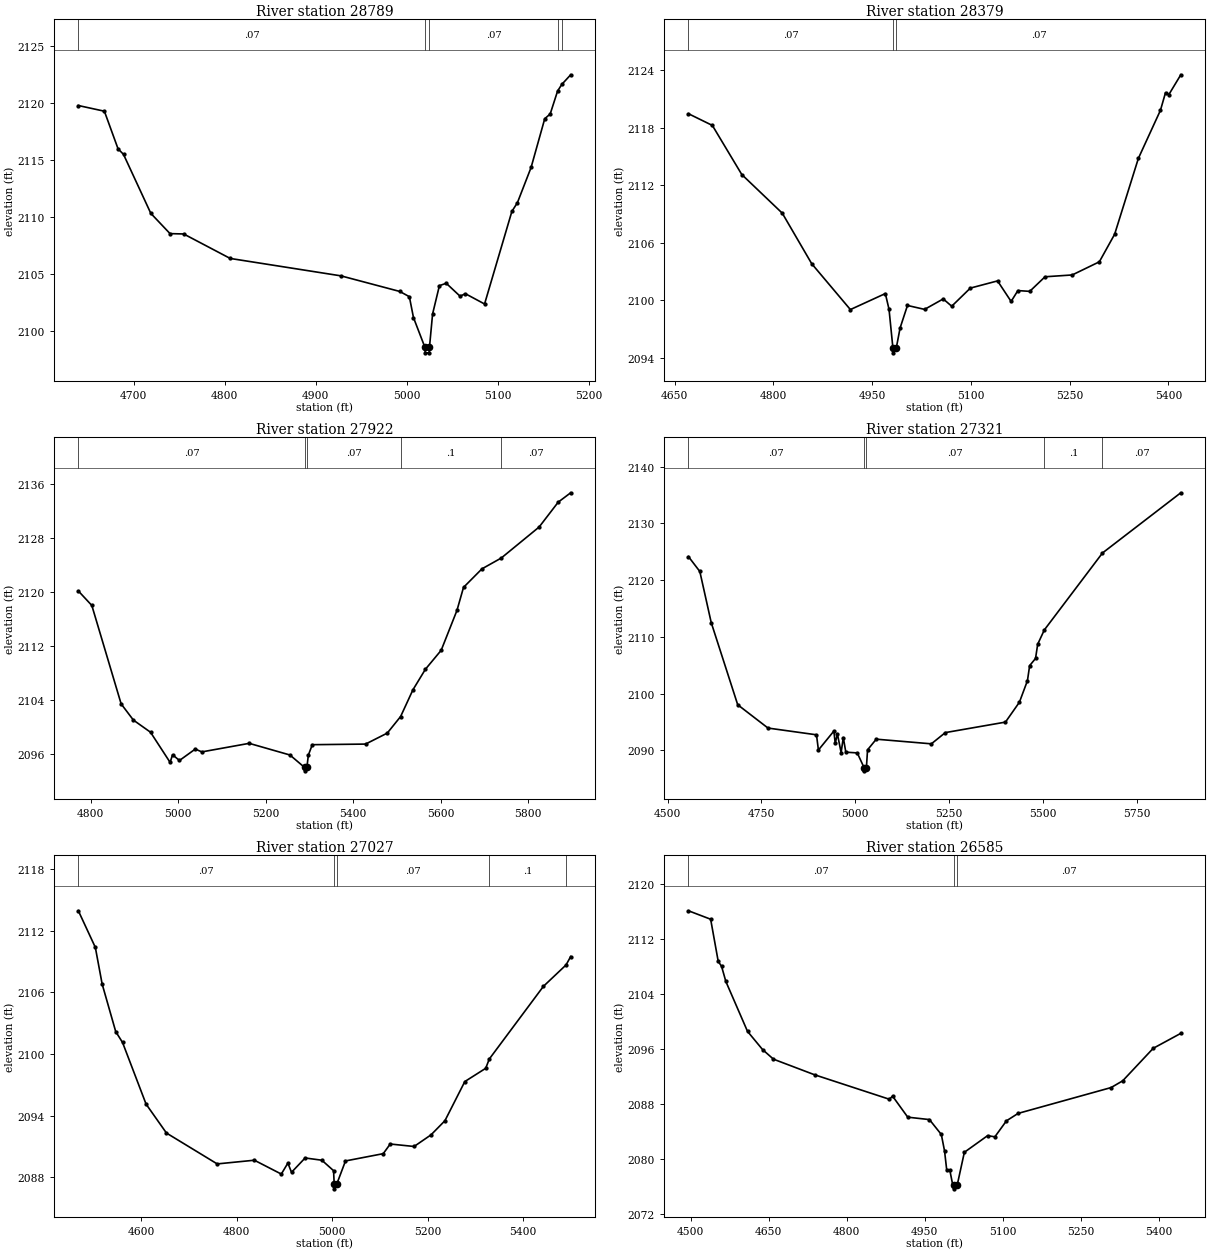
Type RM Length L Ch R = 1 ,28789   ,410,410,410
BEGIN DESCRIPTION:
Rough Hallow 55.0
END DESCRIPTION:
XS GIS Cut Line= 3
      1847025.01     13996425.01        1846725.       13996225.
      1846575.04     13996125.03
#Sta/Elev= 30
  4639.2 2119.77  4667.8 2119.27  4682.8 2115.97  4688.8 2115.48  4718.8  2110.3
  4739.9 2108.52  4754.9 2108.49    4806 2106.34  4927.7 2104.81  4992.3 2103.44
  5002.8 2102.98  5007.3 2101.15  5019.8 2098.55  5020.2 2098.05  5024.5 2098.05
  5024.9 2098.55  5028.3 2101.46  5035.8 2103.95  5043.3 2104.16  5058.4 2103.03
  5064.4 2103.24  5085.4 2102.34  5115.4 2110.47  5121.5 2111.24  5136.5 2114.33
  5151.5 2118.61  5157.5 2119.03  5165.6 2121.04  5170.3 2121.63    5180 2122.47
#Mann= 5 ,-1 , 0
  4639.2     .07       0  5019.8     .05       0  5024.9     .07       0
  5165.6      .1       0  5170.3     .07       0
Bank Sta=5019.8,5024.9
XS Rating Curve= 0 ,0
Exp/Cntr=0.3,0.1

Type RM Length L Ch R = 1 ,28379   ,457,457,457
BEGIN DESCRIPTION:
Rough Hallow 54.0
END DESCRIPTION:
XS GIS Cut Line= 3
      1847174.98     13996274.97        1847025.       13995975.
      1846624.99       13995875.
#Sta/Elev= 30
  4671.1 2119.45  4707.4 2118.23  4752.1 2113.11  4813.6 2109.08  4858.3 2103.81
    4917 2099.03  4970.1  2100.7  4975.7 2099.06  4981.6 2095.02    4982 2094.52
  4986.7 2095.02  4992.5 2097.11  5003.7 2099.46  5029.7 2099.05    5058 2100.14
  5070.9 2099.38  5099.2 2101.27  5140.5 2102.02  5161.1 2099.88  5171.4 2101.01
  5189.4 2100.93  5212.6 2102.45  5253.9 2102.64  5295.1 2104.01  5318.3 2106.88
  5354.4  2114.8  5387.9 2119.81  5395.6 2121.65  5400.7 2121.45  5418.8 2123.51
#Mann= 3 ,-1 , 0
  4671.1     .07       0  4981.6     .05       0  4986.7     .07       0
Bank Sta=4981.6,4986.7
XS Rating Curve= 0 ,0
Exp/Cntr=0.3,0.1

Type RM Length L Ch R = 1 ,27922   ,601,601,601
BEGIN DESCRIPTION:
Rough Hallow 53.0
END DESCRIPTION:
XS GIS Cut Line= 3
      1847525.01     13996025.02        1847425.       13995825.
      1846925.01     13995075.01
#Sta/Elev= 30
  4772.1 2120.12  4802.9 2117.97  4869.9 2103.36  4897.9 2100.96    4937 2099.16
  4981.8 2094.68  4987.3 2095.81  5003.2 2094.97  5039.3 2096.66  5054.3 2096.24
  5162.5 2097.51  5255.6 2095.78  5289.1 2093.93  5289.5 2093.43  5294.3 2093.93
  5297.7 2095.77  5306.7 2097.31  5428.4  2097.4    5478 2099.03  5508.5 2101.49
  5536.6 2105.45  5565.1  2108.5  5601.2 2111.32  5637.2 2117.23  5652.2 2120.65
  5694.3  2123.4  5738.5 2125.01    5825 2129.61  5868.6  2133.3  5897.1 2134.69
#Mann= 5 ,-1 , 0
  4772.1     .07       0  5289.1     .05       0  5294.3     .07       0
  5508.5      .1       0  5738.5     .07       0
Bank Sta=5289.1,5294.3
XS Rating Curve= 0 ,0
Exp/Cntr=0.3,0.1

Type RM Length L Ch R = 1 ,27321   ,294,294,294
BEGIN DESCRIPTION:
Rough Hallow 52.0
END DESCRIPTION:
XS GIS Cut Line= 3
        1847875.     13995825.03      1847824.72     13995443.62
      1847025.02     13994975.01
#Sta/Elev= 30
  4555.7 2124.16    4586 2121.54  4616.3 2112.54  4686.9 2098.05  4767.6 2093.94
  4896.8 2092.75  4901.9 2090.07  4943.1 2093.41  4946.7 2091.25  4952.5  2092.9
  4962.4 2089.63  4968.2 2092.27  4974.9 2089.69  5005.4 2089.56    5024  2086.9
  5024.5  2086.4  5029.7  2086.9  5032.8  2090.1    5056 2091.98  5202.8 2091.16
    5240 2093.14  5400.2 2094.99  5437.4  2098.5  5458.8  2102.3  5464.6 2104.94
  5480.3 2106.21  5486.1 2108.72  5503.7 2111.23  5658.7  2124.8  5867.3 2135.41
#Mann= 5 ,-1 , 0
  4555.7     .07       0    5024     .05       0  5029.7     .07       0
  5503.7      .1       0  5658.7     .07       0
Bank Sta=5024,5029.7
XS Rating Curve= 0 ,0
Exp/Cntr=0.3,0.1

Type RM Length L Ch R = 1 ,27027   ,442,442,442
BEGIN DESCRIPTION:
Rough Hallow 51.0
END DESCRIPTION:
XS GIS Cut Line= 3
      1848275.02     13995575.03        1847925.       13995175.
      1847525.04     13994875.03
#Sta/Elev= 30
  4468.2 2113.96  4503.8 2110.39  4518.1 2106.81  4546.5 2102.18  4560.8 2101.12
  4610.1 2095.11  4652.8 2092.29  4759.1 2089.28    4837 2089.64  4893.4 2088.29
  4907.2 2089.36  4914.8 2088.46  4943.3 2089.86  4978.4 2089.64  5002.9 2088.62
  5004.2 2087.35  5004.6 2086.85  5009.9 2087.35  5027.9 2089.57    5107 2090.28
  5121.6 2091.22  5171.6 2090.98    5207 2092.11  5236.2 2093.49  5277.9 2097.31
  5321.6  2098.6  5329.2 2099.51  5442.5 2106.59    5490 2108.68  5499.7  2109.5
#Mann= 5 ,-1 , 0
  4468.2     .07       0  5004.2     .05       0  5009.9     .07       0
  5329.2      .1       0    5490     .07       0
Bank Sta=5004.2,5009.9
XS Rating Curve= 0 ,0
Exp/Cntr=0.3,0.1

Type RM Length L Ch R = 1 ,26585   ,448,448,448
BEGIN DESCRIPTION:
Rough Hallow 50.0
END DESCRIPTION:
XS GIS Cut Line= 3
      1848575.01     13995325.02        1848275.       13994925.
      1847875.03     13994725.02
#Sta/Elev= 30
  4495.7 2116.15  4538.4 2114.92    4553 2108.77  4559.3 2108.09  4567.6 2105.87
  4609.3  2098.6  4638.4 2095.94  4659.3 2094.55  4738.4 2092.28  4882.2 2088.72
  4888.4 2089.17  4917.6 2086.11  4959.3 2085.76  4982.2 2083.59  4988.4 2081.19
  4992.6  2078.4  4998.5  2078.4  5004.1 2076.27  5006.8 2076.18  5007.2 2075.68
  5012.6 2076.18  5026.5    2081  5071.2 2083.42  5085.2 2083.25  5107.5 2085.58
  5129.9 2086.66  5308.8 2090.42  5331.1  2091.4  5389.8 2096.13  5442.9 2098.31
#Mann= 3 ,-1 , 0
  4495.7     .07       0  5006.8     .05       0  5012.6     .07       0
Bank Sta=5006.8,5012.6
XS Rating Curve= 0 ,0
Exp/Cntr=0.3,0.1

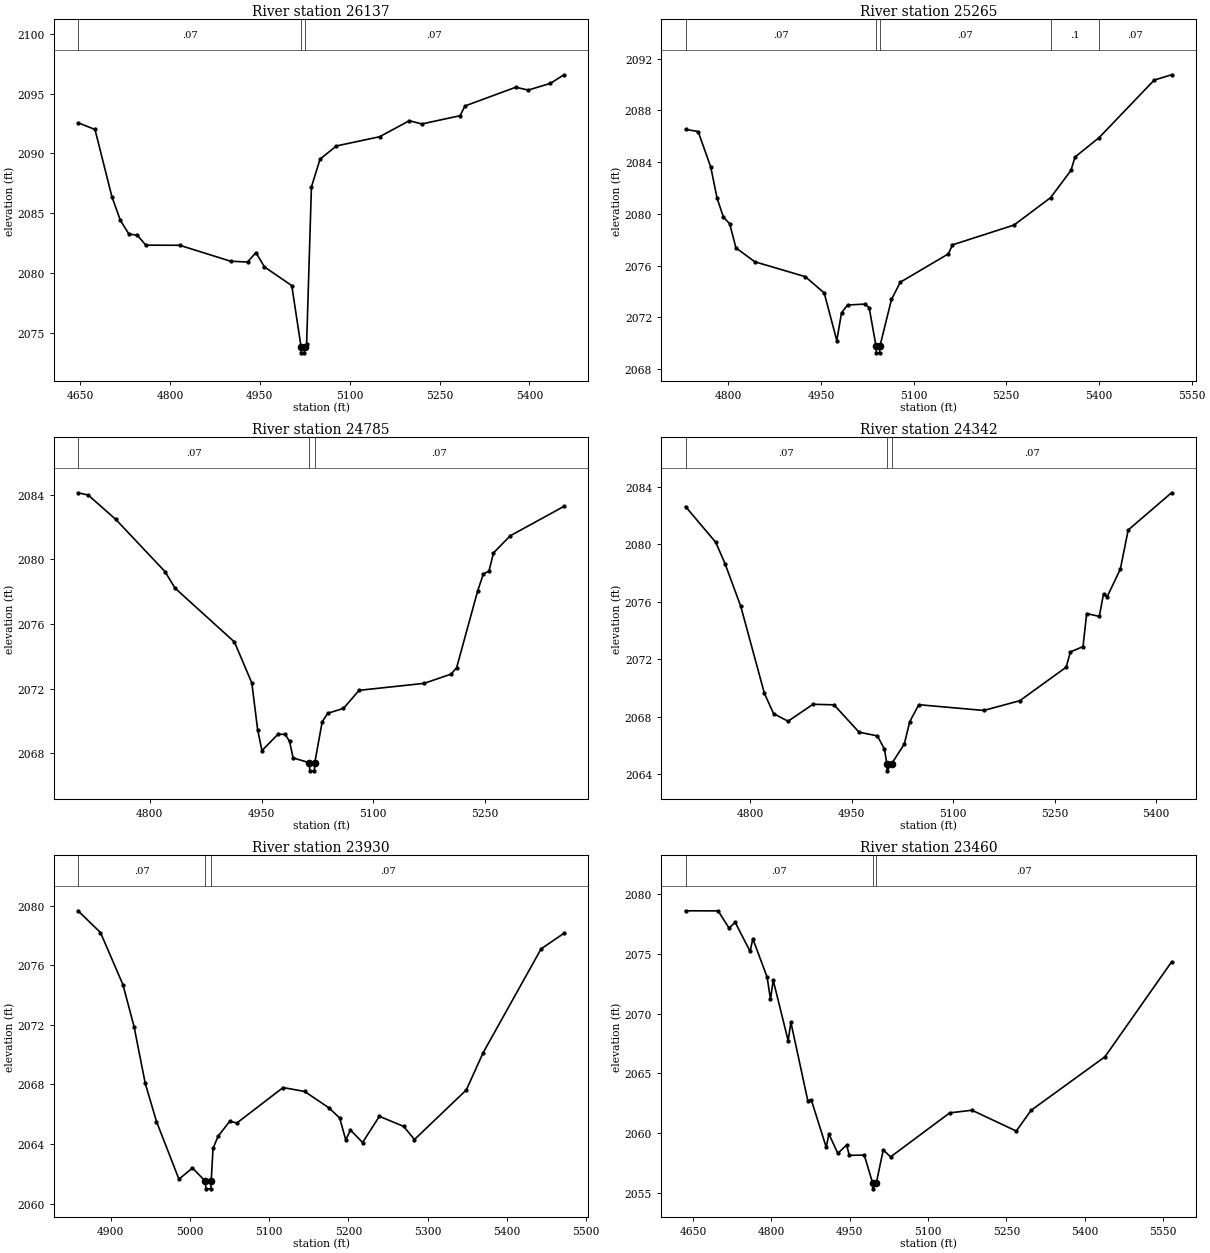
Type RM Length L Ch R = 1 ,26137   ,872,872,872
BEGIN DESCRIPTION:
Rough Hallow 49.0
END DESCRIPTION:
XS GIS Cut Line= 3
      1848675.02     13994825.02        1848425.       13994575.
      1848067.18     13994289.74
#Sta/Elev= 30
  4646.6 2092.56  4674.9    2092  4703.2 2086.37  4717.3  2084.4  4731.5 2083.26
  4745.6 2083.16  4759.8 2082.33  4816.3 2082.32  4901.2 2080.99  4929.5 2080.92
  4943.6 2081.71  4957.8 2080.51  5003.4 2078.95  5018.9 2073.83  5019.4 2073.33
  5024.3 2073.33  5024.8 2073.83  5028.2 2074.09  5036.2 2087.19  5050.6 2089.52
  5077.8 2090.62  5149.9 2091.39  5199.6 2092.73  5220.4 2092.46  5284.4 2093.15
  5292.4 2093.96  5377.3 2095.53  5398.1 2095.29    5435 2095.85  5457.8 2096.57
#Mann= 3 ,-1 , 0
  4646.6     .07       0  5018.9     .05       0  5024.8     .07       0
Bank Sta=5018.9,5024.8
XS Rating Curve= 0 ,0
Exp/Cntr=0.3,0.1

Type RM Length L Ch R = 1 ,25265   ,480,480,480
BEGIN DESCRIPTION:
Rough Hallow 48.0
END DESCRIPTION:
XS GIS Cut Line= 3
        1849175.     13994425.01        1849125.       13994175.
      1848774.98     13993774.98
#Sta/Elev= 30
  4730.9 2086.54  4751.3 2086.37  4771.7 2083.62  4781.9 2081.22  4792.1 2079.76
  4802.3 2079.24  4812.5 2077.37  4843.1  2076.3  4924.7 2075.15  4955.3 2073.89
  4975.7 2070.21  4983.3 2072.35    4993 2072.96  5021.5 2073.03  5028.1 2072.75
  5039.2 2069.76  5039.7 2069.26  5044.9 2069.26  5045.4 2069.76  5064.2 2073.39
  5078.4 2074.72  5156.2 2076.91  5162.9 2077.61  5262.5 2079.14  5321.7 2081.26
  5354.6 2083.36  5361.2  2084.4  5400.4 2085.91  5489.4 2090.35  5517.4 2090.76
#Mann= 5 ,-1 , 0
  4730.9     .07       0  5039.2     .05       0  5045.4     .07       0
  5321.7      .1       0  5400.4     .07       0
Bank Sta=5039.2,5045.4
XS Rating Curve= 0 ,0
Exp/Cntr=0.3,0.1

Type RM Length L Ch R = 1 ,24785   ,443,443,443
BEGIN DESCRIPTION:
Rough Hallow 47.0
END DESCRIPTION:
XS GIS Cut Line= 3
        1849675.       13994025.        1849425.       13993875.
        1849125.       13993675.
#Sta/Elev= 30
  4703.8 2084.11  4717.4 2083.97  4754.3 2082.47  4820.4 2079.24    4834 2078.21
  4913.7 2074.88    4937 2072.35  4944.8 2069.46  4950.6 2068.16    4972 2069.17
  4981.7 2069.17  4987.6 2068.74  4992.4 2067.71  5014.3 2067.41  5014.8 2066.91
    5021 2066.91  5021.5 2067.41  5031.4 2069.94  5038.9 2070.47  5059.9 2070.77
    5081 2071.89  5168.1 2072.32  5204.2 2072.89  5211.7 2073.27  5240.2 2078.06
  5247.7 2079.09  5255.2 2079.26  5261.3 2080.39  5283.8 2081.45  5355.9 2083.27
#Mann= 3 ,-1 , 0
  4703.8     .07       0  5014.3     .05       0  5021.5     .07       0
Bank Sta=5014.3,5021.5
XS Rating Curve= 0 ,0
Exp/Cntr=0.3,0.1

Type RM Length L Ch R = 1 ,24342   ,412,412,412
BEGIN DESCRIPTION:
Rough Hallow 46.0
END DESCRIPTION:
XS GIS Cut Line= 3
      1849825.01     13993775.01        1849675.       13993525.
      1849274.96     13993374.99
#Sta/Elev= 30
  4704.1 2082.61  4748.8 2080.12  4762.4 2078.65  4785.7 2075.68  4820.7 2069.62
  4834.3 2068.21  4855.7 2067.68  4892.6 2068.86  4923.7 2068.82  4960.7 2066.92
  4987.9 2066.66  4998.3 2065.74  5001.8 2064.73  5002.3 2064.23    5009 2064.73
  5027.7  2066.1  5035.7 2067.65  5049.1 2068.83  5145.2 2068.43  5198.6 2069.11
  5267.1 2071.44  5273.3  2072.5    5292 2072.87  5297.4 2075.17  5316.1 2074.97
  5322.3 2076.54  5327.6 2076.33  5347.2 2078.26  5358.8 2080.98  5422.9 2083.57
#Mann= 3 ,-1 , 0
  4704.1     .07       0  5001.8     .05       0    5009     .07       0
Bank Sta=5001.8,5009
XS Rating Curve= 0 ,0
Exp/Cntr=0.3,0.1

Type RM Length L Ch R = 1 ,23930   ,470,470,470
BEGIN DESCRIPTION:
Rough Hallow 45.0
END DESCRIPTION:
XS GIS Cut Line= 3
      1850074.99     13993474.99        1849975.       13993375.
      1849575.01     13993125.01
#Sta/Elev= 30
  4858.8 2079.66  4887.1  2078.2  4915.4 2074.71  4929.5 2071.88  4943.6 2068.07
  4957.8 2065.51  4986.1 2061.64  5003.2 2062.39  5019.6 2061.49  5020.1 2060.99
  5026.3 2060.99  5026.8 2061.49  5029.1  2063.7  5035.6 2064.53  5050.3 2065.53
  5059.2 2065.41  5117.5 2067.79  5144.7 2067.53  5175.3 2066.43  5188.9 2065.75
  5196.6 2064.27  5202.5 2064.94  5217.8  2064.1    5239 2065.86  5269.7 2065.18
  5283.2  2064.3  5348.7 2067.63  5369.9 2070.13    5443  2077.1  5471.9 2078.15
#Mann= 3 ,-1 , 0
  4858.8     .07       0  5019.6     .05       0  5026.8     .07       0
Bank Sta=5019.6,5026.8
XS Rating Curve= 0 ,0
Exp/Cntr=0.3,0.1

Type RM Length L Ch R = 1 ,23460   ,840,840,840
BEGIN DESCRIPTION:
Rough Hallow 44.0
END DESCRIPTION:
XS GIS Cut Line= 3
        1850425.     13993425.01        1850325.       13993075.
        1849925.       13992675.
#Sta/Elev= 30
    4636 2078.59  4698.4 2078.58  4719.2 2077.14  4730.9 2077.63  4759.5 2075.19
  4764.7 2076.25    4792 2073.05  4798.5 2071.19  4803.7 2072.78  4832.3 2067.73
  4837.5 2069.27    4870 2062.69  4876.5 2062.79  4905.1 2058.83  4910.3 2059.93
  4927.2 2058.32  4944.1 2059.01  4949.3 2058.15  4977.9 2058.17  4993.8 2055.85
  4994.3 2055.35    5001 2055.85  5014.2  2058.6  5028.3 2058.02  5141.4  2061.7
  5183.9 2061.92  5268.7 2060.18    5297 2061.91  5438.4 2066.39  5565.7 2074.31
#Mann= 3 ,-1 , 0
    4636     .07       0  4993.8     .05       0    5001     .07       0
Bank Sta=4993.8,5001
XS Rating Curve= 0 ,0
Exp/Cntr=0.3,0.1

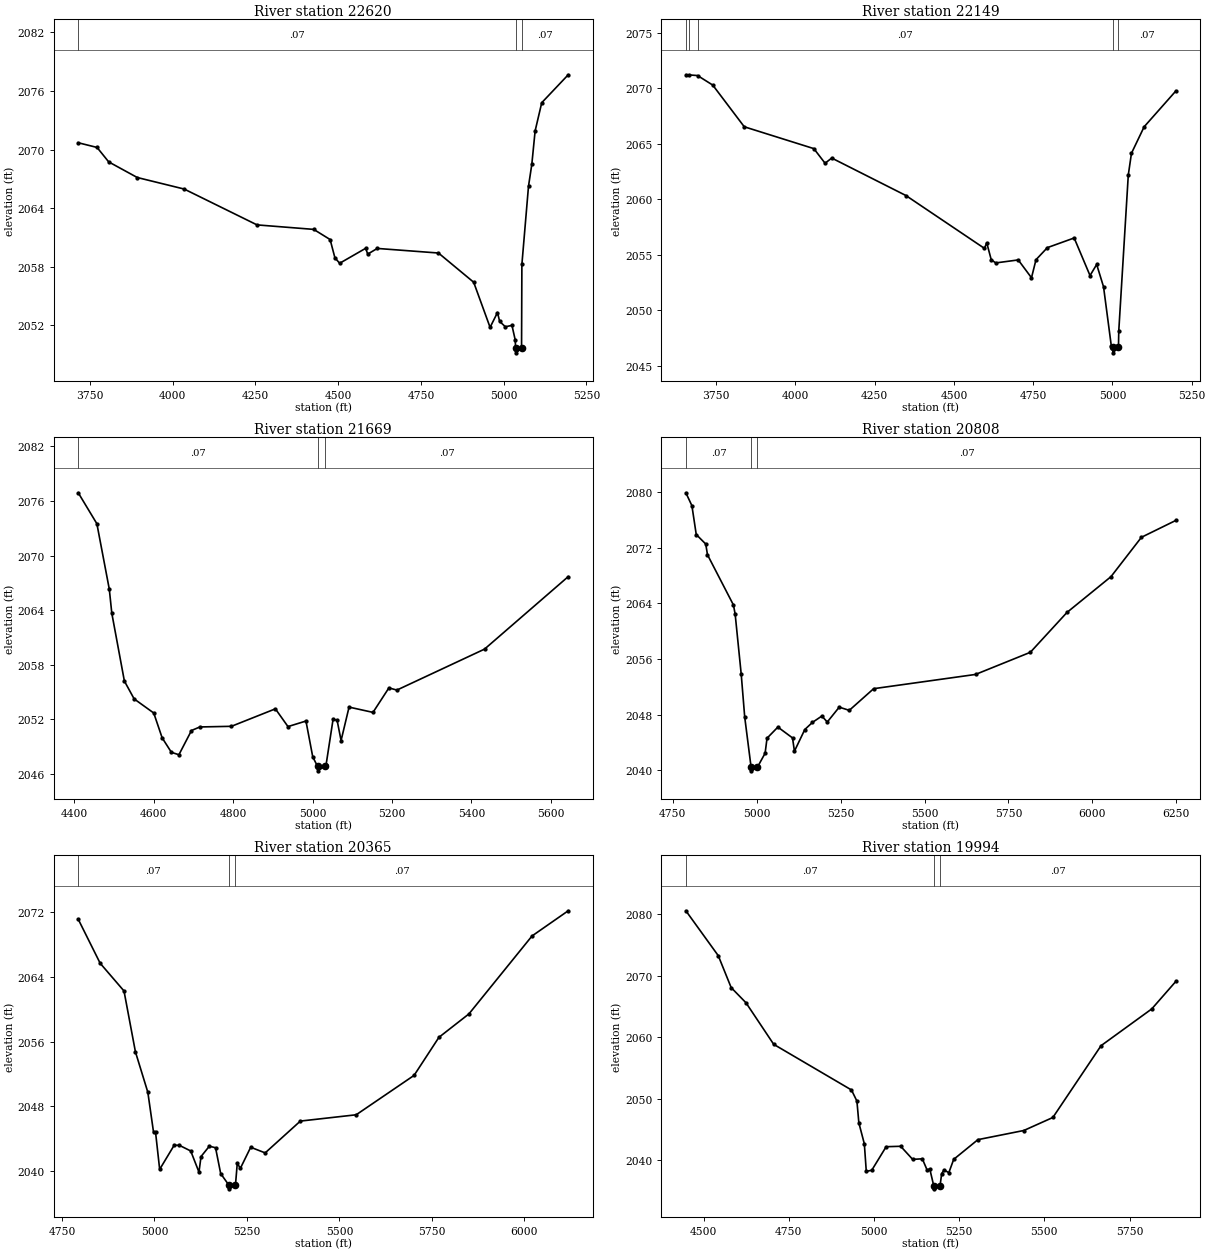
Type RM Length L Ch R = 1 ,22620   ,471,471,471
BEGIN DESCRIPTION:
Rough Hallow 43.0
END DESCRIPTION:
XS GIS Cut Line= 3
      1851225.02     13993175.02        1850225.       13992375.
      1850024.96       13992375.
#Sta/Elev= 30
  3714.3 2070.71  3771.2 2070.23  3806.4 2068.75  3892.8 2067.15  4034.5 2065.97
  4254.6  2062.3  4425.9 2061.84  4475.5  2060.8  4489.9 2058.94  4504.3 2058.37
  4582.8  2059.9  4589.2 2059.31    4618 2059.89  4802.9 2059.42  4909.3 2056.43
  4958.9 2051.81  4981.3 2053.33  4987.8 2052.42    5005 2051.87    5025 2052.01
    5035  2050.5  5035.9  2049.7  5036.4  2049.2    5054  2049.7    5055 2058.25
    5075 2066.26    5085  2068.5    5095 2071.92    5115 2074.81    5195 2077.67
#Mann= 3 ,-1 , 0
  3714.3     .07       0  5035.9     .05       0    5054     .07       0
Bank Sta=5035.9,5054
XS Rating Curve= 0 ,0
Exp/Cntr=0.3,0.1

Type RM Length L Ch R = 1 ,22149   ,480,480,480
BEGIN DESCRIPTION:
Rough Hallow 42.0
END DESCRIPTION:
XS GIS Cut Line= 3
        1851425.       13992875.        1850425.       13991975.
      1850224.96       13991975.
#Sta/Elev= 30
  3654.6 2071.23  3663.4 2071.22  3691.5 2071.16  3739.4  2070.3  3838.8 2066.54
  4058.2 2064.57  4093.7 2063.25  4114.6 2063.72  4348.6 2060.34  4596.4 2055.57
  4603.5 2056.08  4617.7 2054.55  4631.9 2054.26  4702.9 2054.53  4744.7 2052.92
  4758.9 2054.55  4794.8 2055.64  4879.3 2056.51  4929.3 2053.12  4950.3 2054.12
  4971.9 2052.11  4996.6 2046.74  5000.9 2046.65  5001.4 2046.15    5019 2046.65
    5020 2048.14    5050 2062.19    5060 2064.15    5100 2066.54    5200 2069.77
#Mann= 5 ,-1 , 0
  3654.6     .07       0  3663.4      .1       0  3691.5     .07       0
  5000.9     .05       0    5019     .07       0
Bank Sta=5000.9,5019
XS Rating Curve= 0 ,0
Exp/Cntr=0.3,0.1

Type RM Length L Ch R = 1 ,21669   ,861,861,861
BEGIN DESCRIPTION:
Rough Hallow 41.0
END DESCRIPTION:
XS GIS Cut Line= 3
      1851325.01       13991875.      1850761.87     13991682.34
      1850125.03       13991625.
#Sta/Elev= 30
  4409.5 2076.89  4456.5 2073.49  4487.8  2066.3  4494.1 2063.66  4525.8 2056.21
  4550.4 2054.25  4599.8  2052.7  4620.9 2049.98  4644.3 2048.38  4663.2 2048.12
  4694.9 2050.78    4716 2051.17  4795.5 2051.24  4906.3 2053.16    4938 2051.21
  4983.3 2051.82  5000.4 2047.89  5012.4 2046.85  5012.9 2046.35  5030.8 2046.85
  5033.8 2046.95  5051.7 2052.03  5061.8  2051.9  5071.8 2049.68  5091.9 2053.35
  5152.2 2052.77  5192.3 2055.46  5212.4 2055.22  5433.3 2059.72  5644.1 2067.68
#Mann= 3 ,-1 , 0
  4409.5     .07       0  5012.4     .05       0  5030.8     .07       0
Bank Sta=5012.4,5030.8
XS Rating Curve= 0 ,0
Exp/Cntr=0.3,0.1

Type RM Length L Ch R = 1 ,20808   ,443,443,443
BEGIN DESCRIPTION:
Rough Hallow 40.0
END DESCRIPTION:
XS GIS Cut Line= 3
      1851224.95     13991025.01        1851025.       13991075.
        1849925.       13991675.
#Sta/Elev= 30
  4789.3 2079.93  4807.3 2078.07  4820.2 2073.92  4848.5 2072.55  4853.7    2071
    4931 2063.77  4936.1 2062.45  4954.2 2053.77  4964.5 2047.65  4983.6 2040.39
  4984.1 2039.89  5002.1 2040.39  5025.3 2042.43    5031 2044.59  5063.3 2046.19
  5106.9 2044.63  5112.6 2042.72  5143.5 2045.84  5166.3 2046.87  5194.3 2047.78
  5210.4 2046.92    5246 2049.06  5275.9  2048.6  5348.5 2051.72  5651.8 2053.77
  5815.1 2056.96  5924.2  2062.7  6055.2 2067.85  6145.9 2073.52  6248.4 2075.95
#Mann= 3 ,-1 , 0
  4789.3     .07       0  4983.6     .05       0  5002.1     .07       0
Bank Sta=4983.6,5002.1
XS Rating Curve= 0 ,0
Exp/Cntr=0.3,0.1

Type RM Length L Ch R = 1 ,20365   ,371,371,371
BEGIN DESCRIPTION:
Rough Hallow 39.0
END DESCRIPTION:
XS GIS Cut Line= 3
        1850975.       13990675.        1850775.       13990725.
      1849774.99       13991225.
#Sta/Elev= 30
  4794.1 2071.15  4853.4  2065.7  4917.8 2062.27  4948.7 2054.73  4982.2 2049.73
  4997.7 2044.76  5003.1 2044.76  5014.2 2040.18  5053.4 2043.17  5067.3 2043.16
  5098.1 2042.46  5120.4 2039.84    5126 2041.77  5148.4 2043.05  5165.2 2042.86
  5179.1 2039.66  5200.6 2038.27  5201.1 2037.77  5219.1 2038.27  5223.9 2040.93
  5232.3 2040.31  5260.2 2042.92  5299.3 2042.22  5394.4 2046.16  5545.3 2046.94
  5701.8 2051.82  5768.9 2056.53    5850 2059.43  6020.5 2069.08  6118.3  2072.2
#Mann= 3 ,-1 , 0
  4794.1     .07       0  5200.6     .05       0  5219.1     .07       0
Bank Sta=5200.6,5219.1
XS Rating Curve= 0 ,0
Exp/Cntr=0.3,0.1

Type RM Length L Ch R = 1 ,19994   ,547,547,547
BEGIN DESCRIPTION:
Rough Hallow 38.0
END DESCRIPTION:
XS GIS Cut Line= 3
      1850974.97     13990275.02      1850477.18      13990549.3
      1849824.98     13991125.01
#Sta/Elev= 30
  4447.7 2080.57  4542.8 2073.26  4580.7 2068.06  4624.2 2065.59  4705.6 2058.82
  4933.8 2051.39  4949.8 2049.58  4955.5 2046.03  4971.6 2042.62  4977.3 2038.13
  4993.4 2038.32  5035.6 2042.15  5078.3 2042.22  5113.4 2040.09  5141.8 2040.18
  5156.1 2038.32  5163.6 2038.55  5175.3 2035.79  5175.8 2035.29  5193.8 2035.79
  5198.7 2037.78  5205.7 2038.36  5219.6 2037.92  5233.9 2040.09    5305  2043.3
  5439.7 2044.79    5525 2046.91  5666.4  2058.6  5815.3 2064.59    5886 2069.07
#Mann= 3 ,-1 , 0
  4447.7     .07       0  5175.3     .05       0  5193.8     .07       0
Bank Sta=5175.3,5193.8
XS Rating Curve= 0 ,0
Exp/Cntr=0.3,0.1

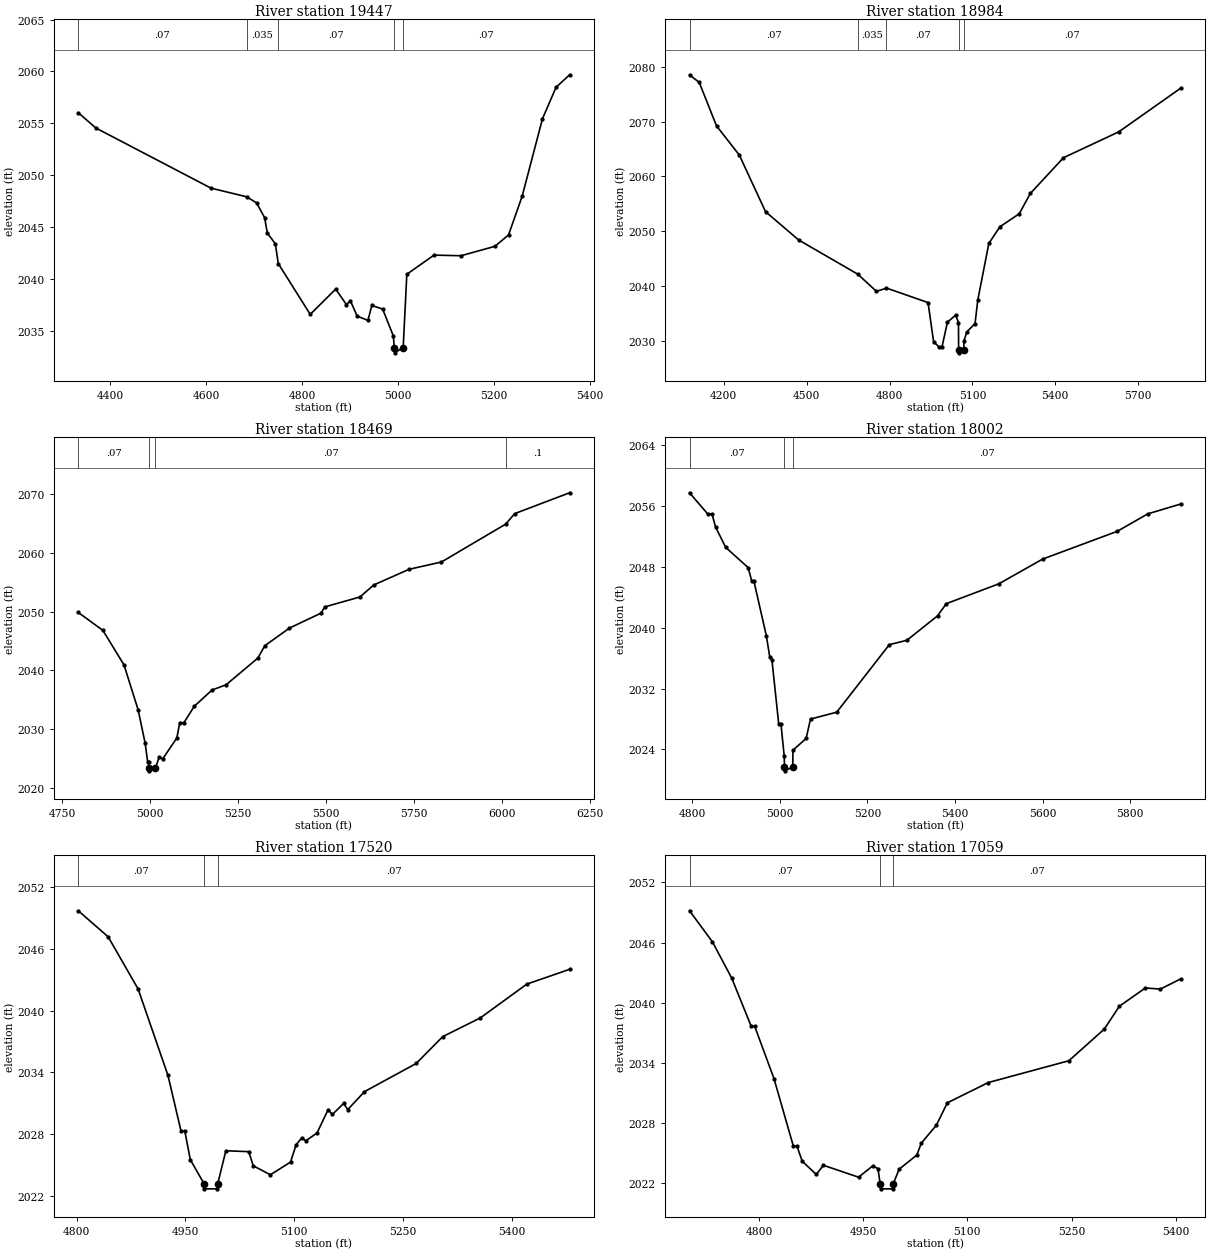
Type RM Length L Ch R = 1 ,19447   ,463,463,463
BEGIN DESCRIPTION:
Rough Hallow 37.0
END DESCRIPTION:
XS GIS Cut Line= 3
      1850625.02     13990224.99        1850025.       13990525.
        1849775.       13990775.
#Sta/Elev= 30
    4333 2056.02  4369.4 2054.55  4609.7 2048.74  4683.8 2047.91  4704.8 2047.32
  4721.5 2045.89  4727.1 2044.41  4743.9 2043.37  4749.9 2041.47  4816.6 2036.56
  4869.7    2039    4892 2037.51  4900.4 2037.87  4914.4  2036.4  4936.8 2035.98
  4945.1 2037.42  4967.5 2037.08  4989.9 2034.48  4991.8 2033.35  4992.3 2032.85
  5010.4 2033.35    5018 2040.43  5074.6 2042.28  5131.1 2042.22  5201.8 2043.13
  5230.1 2044.23  5258.4 2047.95  5300.8 2055.43  5329.1 2058.47  5357.4 2059.68
#Mann= 5 ,-1 , 0
    4333     .07       0  4683.8    .035       0  4749.9     .07       0
  4991.8     .05       0  5010.4     .07       0
Bank Sta=4991.8,5010.4
XS Rating Curve= 0 ,0
Exp/Cntr=0.3,0.1

Type RM Length L Ch R = 1 ,18984   ,515,515,515
BEGIN DESCRIPTION:
Rough Hallow 36.1
END DESCRIPTION:
XS GIS Cut Line= 4
      1850818.72     13989887.71      1850128.34     13990092.27
      1849699.07     13990103.08       1849070.3     13990121.54
#Sta/Elev= 30
  4076.1 2078.51  4111.3 2077.11  4173.8  2069.2  4256.1 2063.91  4351.2 2053.59
  4471.2 2048.43  4685.1 2042.21  4752.8 2039.07    4789 2039.68  4939.5 2037.04
  4959.5 2029.94  4979.5 2028.94  4989.6 2028.87  5009.6 2033.47  5039.6 2034.76
  5049.6 2033.39  5050.2 2028.39  5050.7 2027.89  5068.9 2028.39  5069.6 2030.07
  5079.6 2031.69  5109.6 2033.22  5119.6 2037.52  5159.6 2047.82  5199.6 2050.84
  5269.6 2053.21  5309.7  2056.9  5429.7 2063.41  5629.8 2068.12  5854.6 2076.09
#Mann= 5 ,-1 , 0
  4076.1     .07       0  4685.1    .035       0    4789     .07       0
  5050.2     .05       0  5068.9     .07       0
Bank Sta=5050.2,5068.9
XS Rating Curve= 0 ,0
Exp/Cntr=0.3,0.1

Type RM Length L Ch R = 1 ,18469   ,467,467,467
BEGIN DESCRIPTION:
Rough Hallow 36.0
END DESCRIPTION:
XS GIS Cut Line= 3
      1850475.05       13989725.        1850275.       13989725.
      1849079.31     13989660.04
#Sta/Elev= 30
  4795.8 2049.86  4865.8 2046.81  4925.8 2040.92  4965.8  2033.3  4985.8 2027.62
  4993.3 2024.32  4995.8 2024.32  4996.5 2023.35    4997 2022.85  5015.3 2023.35
  5025.9 2025.19  5035.9 2024.89    5076 2028.44  5084.5 2031.08    5096 2031.04
    5126 2033.88  5176.1 2036.63  5216.2 2037.53  5306.3 2042.07  5326.3 2044.19
  5396.4  2047.2  5486.6 2049.76  5496.6 2050.81  5596.7  2052.5  5636.4 2054.56
  5736.9 2057.23  5828.7 2058.47  6011.1 2064.92  6037.4 2066.73  6193.3 2070.28
#Mann= 4 ,-1 , 0
  4795.8     .07       0  4996.5     .05       0  5015.3     .07       0
  6011.1      .1       0
Bank Sta=4996.5,5015.3
XS Rating Curve= 0 ,0
Exp/Cntr=0.3,0.1

Type RM Length L Ch R = 1 ,18002   ,482,482,482
BEGIN DESCRIPTION:
Rough Hallow 35.0
END DESCRIPTION:
XS GIS Cut Line= 3
      1850525.02     13989325.01        1850325.       13989275.
      1849409.48     13989288.78
#Sta/Elev= 30
  4793.9 2057.72  4835.2 2054.95  4845.5 2054.89  4853.2 2053.24  4876.4 2050.55
  4927.9 2047.88  4935.7 2046.15  4940.8 2046.14  4969.2 2038.95  4976.9 2036.21
    4982 2035.77  4997.5 2027.36  5002.6 2027.36  5010.1 2023.11  5010.7 2021.69
  5011.2 2021.19  5029.5 2021.69  5030.1  2023.9  5060.1 2025.45  5070.1 2027.99
  5130.1  2028.9  5250.1 2037.77  5290.1 2038.34  5360.1 2041.55  5380.1 2043.15
  5500.1 2045.76  5600.1 2049.01  5770.2 2052.65  5840.2 2054.95  5915.7 2056.25
#Mann= 3 ,-1 , 0
  4793.9     .07       0  5010.7     .05       0  5029.5     .07       0
Bank Sta=5010.7,5029.5
XS Rating Curve= 0 ,0
Exp/Cntr=0.3,0.1

Type RM Length L Ch R = 1 ,17520   ,461,461,461
BEGIN DESCRIPTION:
Rough Hallow 34.0
END DESCRIPTION:
XS GIS Cut Line= 3
      1850425.01       13988775.        1850225.       13988825.
      1849824.97     13989075.02
#Sta/Elev= 30
  4802.2 2049.66  4843.4 2047.14  4884.7 2042.09  4925.9 2033.72  4943.9 2028.34
  4949.1 2028.34  4956.8 2025.55  4975.7 2023.23  4976.2 2022.73  4994.1 2022.73
  4994.6 2023.23  5005.8 2026.42  5037.3 2026.33  5043.7 2024.96  5067.3 2024.09
    5095 2025.32  5102.7 2026.99  5110.4 2027.66  5116.3 2027.39  5131.6 2028.14
  5146.9  2030.4  5152.8 2029.93  5168.2    2031  5174.1 2030.41    5197 2032.14
  5268.4 2034.87    5305 2037.47  5356.8 2039.28  5421.1 2042.56  5480.1 2043.99
#Mann= 3 ,-1 , 0
  4802.2     .07       0  4975.7     .05       0  4994.6     .07       0
Bank Sta=4975.7,4994.6
XS Rating Curve= 0 ,0
Exp/Cntr=0.3,0.1

Type RM Length L Ch R = 1 ,17059   ,450,450,450
BEGIN DESCRIPTION:
Rough Hallow 33.0
END DESCRIPTION:
XS GIS Cut Line= 3
      1850424.98       13988475.        1850125.       13988425.
      1849775.03     13988624.98
#Sta/Elev= 30
  4700.1 2049.16    4733 2046.07  4760.9 2042.44  4788.8 2037.66  4793.9 2037.65
  4821.7 2032.43  4849.6  2025.7  4854.7 2025.73  4862.3 2024.21  4882.6 2022.89
  4892.7 2023.81  4943.4 2022.62  4963.7 2023.74  4971.3 2023.48  4974.5 2021.96
    4975 2021.46  4992.9 2021.46  4993.4 2021.96  5001.7 2023.41  5027.3 2024.83
  5033.7 2026.01  5055.3 2027.79  5071.2 2030.03  5130.2 2032.05  5246.1 2034.22
  5297.2 2037.38  5318.8 2039.65  5356.2 2041.47  5377.8 2041.36  5407.3 2042.38
#Mann= 3 ,-1 , 0
  4700.1     .07       0  4974.5     .05       0  4993.4     .07       0
Bank Sta=4974.5,4993.4
XS Rating Curve= 0 ,0
Exp/Cntr=0.3,0.1

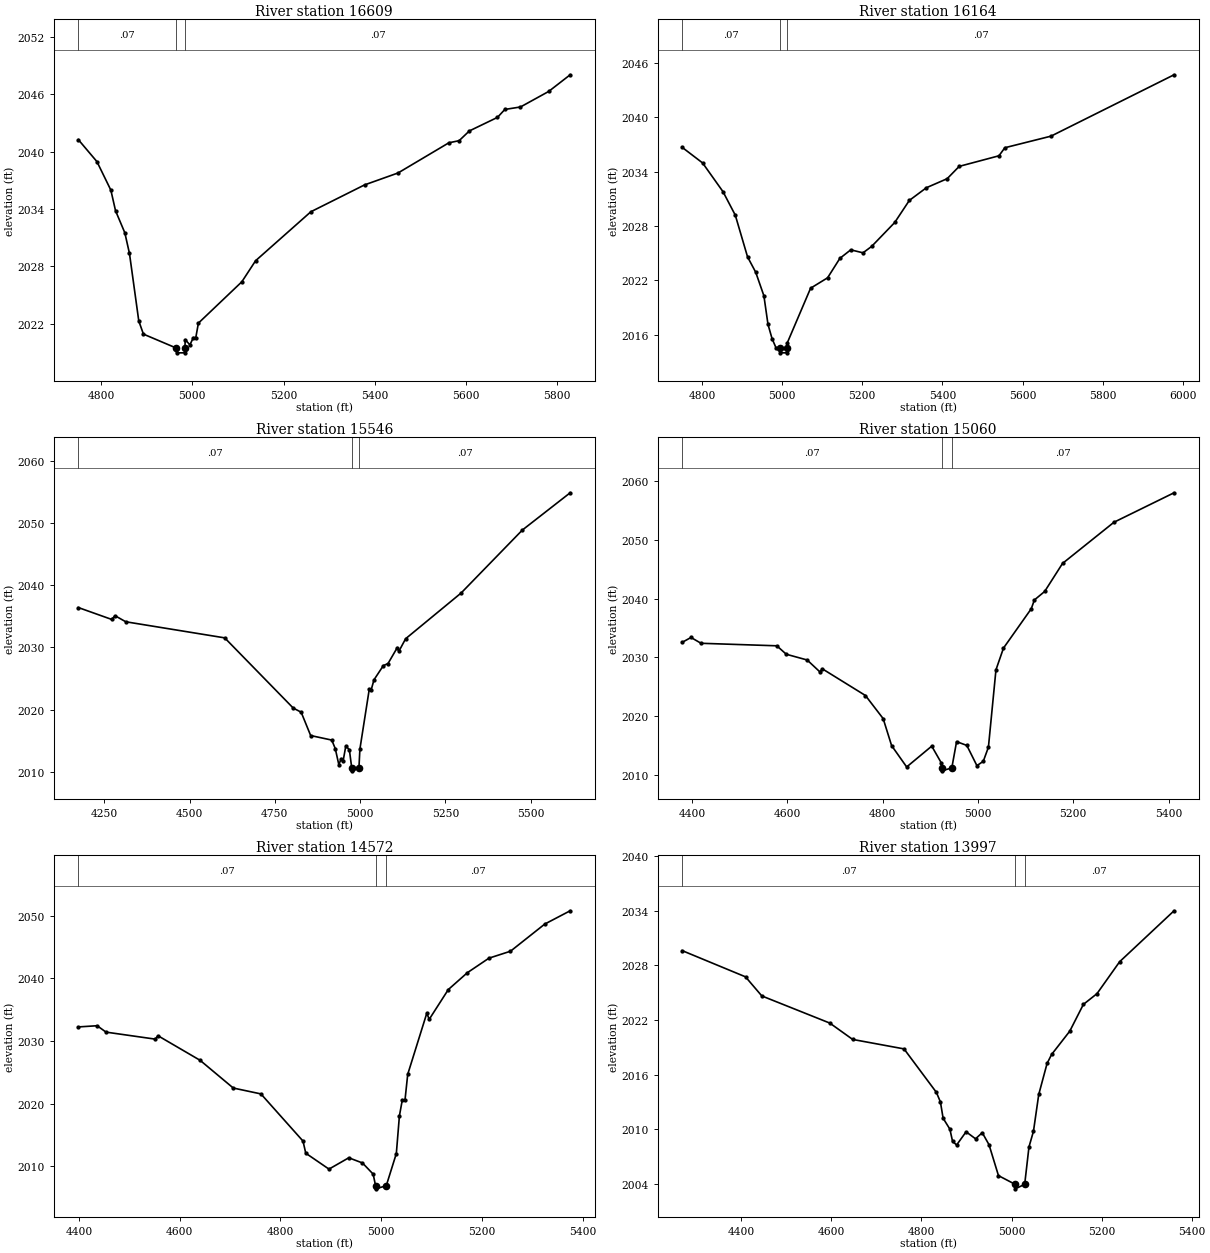
Type RM Length L Ch R = 1 ,16609   ,445,445,445
BEGIN DESCRIPTION:
Rough Hallow 32.0
END DESCRIPTION:
XS GIS Cut Line= 3
      1850324.99       13987975.        1850075.       13988025.
      1849336.53     13988390.48
#Sta/Elev= 30
  4749.9 2041.27  4790.7 2038.97  4821.3 2035.98  4831.5 2033.83  4851.9 2031.52
  4862.1 2029.35  4882.5 2022.29  4892.7 2020.91  4964.8 2019.45  4965.3 2018.95
  4983.2 2018.95  4983.7 2019.45  4984.4 2020.34  4994.6 2019.78  5002.3 2020.55
  5007.6 2020.55  5013.3 2022.06  5108.6 2026.39  5138.7 2028.59    5260 2033.72
  5377.7 2036.53  5451.2 2037.78  5562.7 2040.94  5585.2 2041.16  5607.6 2042.18
  5669.3  2043.6  5685.5 2044.43  5719.8 2044.69  5781.5 2046.31  5828.8 2048.06
#Mann= 3 ,-1 , 0
  4749.9     .07       0  4964.8     .05       0  4983.7     .07       0
Bank Sta=4964.8,4983.7
XS Rating Curve= 0 ,0
Exp/Cntr=0.3,0.1

Type RM Length L Ch R = 1 ,16164   ,618,618,618
BEGIN DESCRIPTION:
Rough Hallow 31.0
END DESCRIPTION:
XS GIS Cut Line= 4
      1850274.95     13987674.99        1850025.       13987625.
        1849625.       13987875.      1849219.81     13988169.13
#Sta/Elev= 30
  4750.8 2036.69  4801.7 2034.97  4852.7 2031.79  4883.3  2029.2  4913.9 2024.59
  4934.3 2022.89  4954.7 2020.29  4964.9 2017.13  4975.1 2015.55  4985.3 2014.51
  4993.7 2014.49  4994.2 2013.99  5012.1 2013.99  5012.6 2014.49  5013.4 2015.13
  5071.2 2021.13  5113.6 2022.28  5144.3 2024.43  5171.4 2025.37    5202 2025.04
  5223.3 2025.74  5281.1 2028.39  5317.6 2030.83  5360.1 2032.23    5412 2033.23
    5442 2034.59  5541.2 2035.76  5555.9 2036.65  5671.1 2037.93  5978.1 2044.71
#Mann= 3 ,-1 , 0
  4750.8     .07       0  4993.7     .05       0  5012.6     .07       0
Bank Sta=4993.7,5012.6
XS Rating Curve= 0 ,0
Exp/Cntr=0.3,0.1

Type RM Length L Ch R = 1 ,15546   ,486,486,486
BEGIN DESCRIPTION:
Rough Hallow 30.1
END DESCRIPTION:
XS GIS Cut Line= 4
      1850642.24     13987103.37      1849996.57     13987039.37
      1849610.21     13987137.11      1849215.56     13987156.76
#Sta/Elev= 30
  4173.7 2036.42  4271.4 2034.51  4281.5  2035.1  4312.9 2034.13    4603 2031.54
    4804 2020.24  4827.2 2019.58  4855.1 2015.82    4917 2015.09  4927.3 2013.71
  4937.6 2011.16  4945.1  2012.1  4950.3 2011.74  4958.2 2014.13  4968.6 2013.53
  4975.5 2010.64    4976 2010.14  4996.7 2010.64  4999.5 2013.64  5027.1 2023.32
  5032.3 2023.11  5040.8 2024.79  5068.2 2027.07    5082 2027.41  5109.2 2029.98
  5114.3 2029.43  5133.6  2031.4  5296.4 2038.76  5475.9 2048.89  5616.2 2054.89
#Mann= 3 ,-1 , 0
  4173.7     .07       0  4975.5     .05       0  4996.7     .07       0
Bank Sta=4975.5,4996.7
XS Rating Curve= 0 ,0
Exp/Cntr=0.3,0.1

Type RM Length L Ch R = 1 ,15060   ,488,488,488
BEGIN DESCRIPTION:
Rough Hallow 30.0
END DESCRIPTION:
XS GIS Cut Line= 3
      1850422.54     13986820.43        1849825.       13986625.
        1849475.       13986425.
#Sta/Elev= 30
  4379.7 2032.58  4398.2 2033.41  4419.2 2032.42  4578.2 2031.99  4598.1 2030.55
  4641.9 2029.57  4668.5 2027.55  4673.8 2028.06  4764.1 2023.52  4801.3 2019.58
    4819 2014.98  4850.6 2011.34  4903.2 2014.89  4923.5    2012  4924.1 2011.18
  4924.6 2010.68  4945.3 2011.18  4955.3 2015.66  4976.8 2015.01  4997.9 2011.57
  5011.3  2012.3  5022.1 2014.71  5037.9 2027.89  5053.7  2031.6    5112 2038.31
  5118.5  2039.8  5140.1 2041.25  5177.6 2046.03  5285.5 2053.05  5411.5 2058.07
#Mann= 3 ,-1 , 0
  4379.7     .07       0  4924.1     .05       0  4945.3     .07       0
Bank Sta=4924.1,4945.3
XS Rating Curve= 0 ,0
Exp/Cntr=0.3,0.1

Type RM Length L Ch R = 1 ,14572   ,575,575,575
BEGIN DESCRIPTION:
Rough Hallow 29.0
END DESCRIPTION:
XS GIS Cut Line= 4
      1850325.02     13986725.04      1850109.97     13986251.93
      1850000.33     13986184.33      1849674.96     13986225.01
#Sta/Elev= 30
  4398.9 2032.25  4436.3 2032.44  4453.9 2031.42  4551.6  2030.3  4557.1 2030.84
  4640.6 2026.92  4706.5 2022.49  4761.4 2021.55  4844.9 2014.02  4850.4 2012.08
  4896.5 2009.54  4935.8 2011.35    4963 2010.52  4984.2 2008.74    4989 2006.89
  4989.5 2006.39  5010.2 2006.89  5030.2 2012.03  5036.3 2018.04    5042 2020.57
  5047.4 2020.57  5052.8 2024.68  5090.6 2034.42  5095.6 2033.48  5133.4 2038.22
  5171.2 2040.91    5214 2043.23  5256.8 2044.34  5324.9 2048.68  5375.3  2050.8
#Mann= 3 ,-1 , 0
  4398.9     .07       0    4989     .05       0  5010.2     .07       0
Bank Sta=4989,5010.2
XS Rating Curve= 0 ,0
Exp/Cntr=0.3,0.1

Type RM Length L Ch R = 1 ,13997   ,585,585,585
BEGIN DESCRIPTION:
Rough Hallow 28.0
END DESCRIPTION:
XS GIS Cut Line= 3
      1850793.42     13986371.48      1850384.62     13985766.71
      1850025.01       13985725.
#Sta/Elev= 30
  4268.8 2029.63  4409.4 2026.75  4445.6 2024.65  4596.4 2021.67  4647.3 2019.87
  4761.3 2018.83  4833.2 2014.05  4842.1    2013  4848.1 2011.21  4863.1 2010.01
  4869.1 2008.66  4878.1 2008.27  4899.1 2009.72  4920.1 2008.95    4935 2009.62
    4950  2008.3    4971  2004.9  5007.9 2003.95  5008.4 2003.45  5029.2 2003.95
  5038.7 2008.05  5048.7 2009.78  5060.4 2013.82  5078.9 2017.23    5089 2018.22
  5129.3 2020.78  5159.5 2023.72  5189.7  2024.9    5240 2028.41  5360.8 2034.01
#Mann= 3 ,-1 , 0
  4268.8     .07       0  5007.9     .05       0  5029.2     .07       0
Bank Sta=5007.9,5029.2
XS Rating Curve= 0 ,0
Exp/Cntr=0.3,0.1