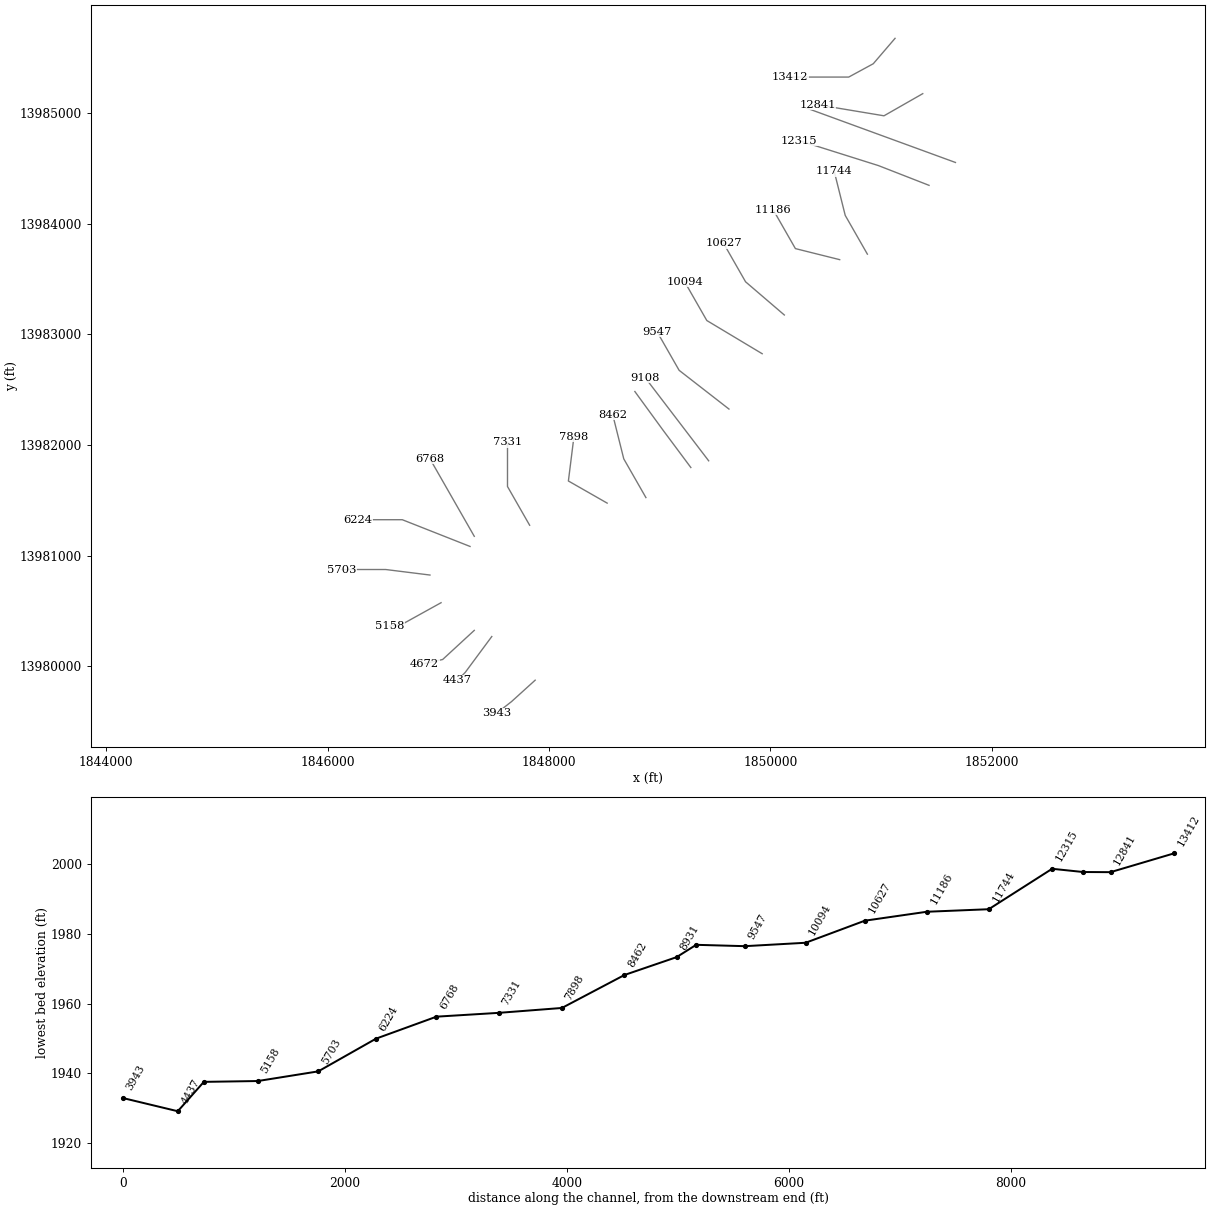
HEC-RAS study Rough Hollow.prj: Rough Hollow Base Level Engineering

--- Rough Hollow.g01 (geometry) --- (continued)

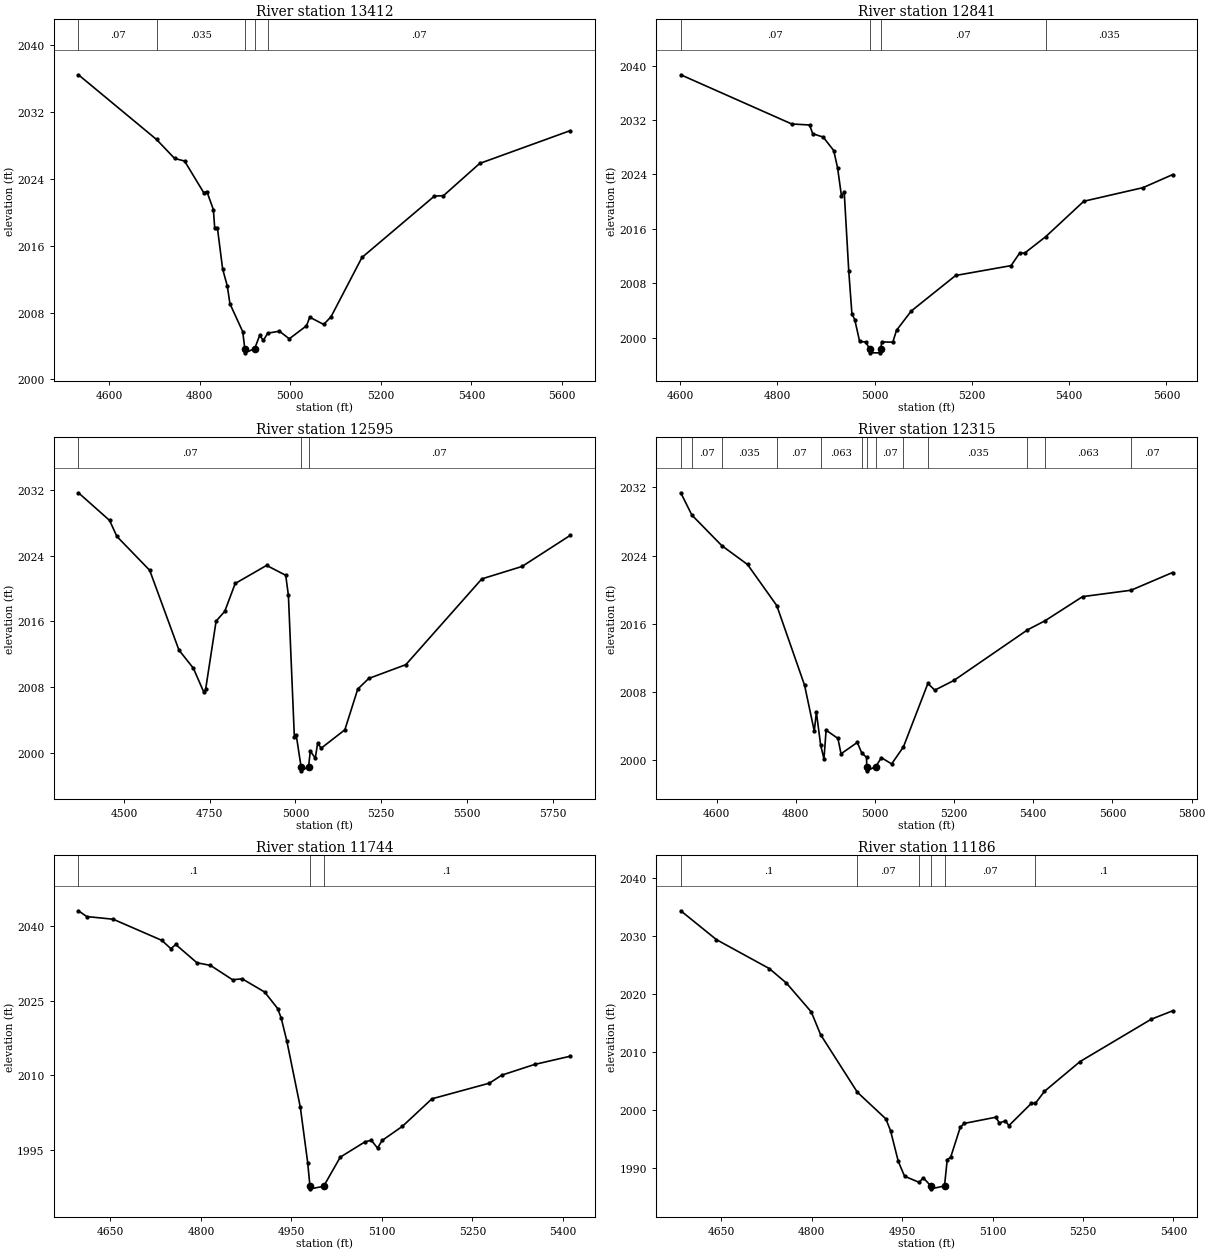
Type RM Length L Ch R = 1 ,13412   ,571,571,571
BEGIN DESCRIPTION:
Rough Hallow 27.0
END DESCRIPTION:
XS GIS Cut Line= 4
      1851125.02     13985675.02      1850928.29      13985445.5
      1850706.64       13985325.      1850175.02       13985325.
#Sta/Elev= 30
  4532.2 2036.47  4704.7 2028.72  4744.6 2026.45  4766.6 2026.14  4808.8 2022.36
  4815.9 2022.48  4830.2 2020.33  4833.2  2018.1  4839.2  2018.1  4850.7 2013.21
    4861 2011.17  4866.8 2009.05  4895.1  2005.7  4899.6 2003.67  4900.1 2003.17
  4921.4 2003.67  4932.4 2005.25  4940.7 2004.66  4950.3 2005.53  4976.1 2005.76
  4997.9 2004.85  5035.9 2006.41  5043.1 2007.44  5073.9 2006.57  5090.1 2007.49
  5158.4 2014.59  5318.4 2021.94  5338.4 2021.99  5418.4 2025.85  5618.4 2029.78
#Mann= 5 ,-1 , 0
  4532.2     .07       0  4704.7    .035       0  4899.6     .05       0
  4921.4    .035       0  4950.3     .07       0
Bank Sta=4899.6,4921.4
XS Rating Curve= 0 ,0
Exp/Cntr=0.3,0.1

Type RM Length L Ch R = 1 ,12841   ,246,246,246
BEGIN DESCRIPTION:
Rough Hallow 26.0
END DESCRIPTION:
XS GIS Cut Line= 3
      1851375.02     13985175.01        1851025.       13984975.
      1850425.01       13985075.
#Sta/Elev= 30
  4601.2 2038.65  4829.4 2031.42  4866.1 2031.27  4872.6 2029.99  4894.2 2029.49
  4915.8 2027.51  4923.7 2024.97  4931.6 2020.89  4937.4 2021.38  4946.7 2009.81
  4953.2 2003.52    4959 2002.67  4969.1 1999.45  4981.3 1999.38  4990.6 1998.28
  4991.1 1997.78  5011.9 1997.78  5012.4 1998.28  5014.5 1999.38  5037.3 1999.35
  5044.9 2001.09  5075.3 2003.93  5166.5 2009.15  5280.6  2010.6  5298.3 2012.46
  5308.5 2012.44    5352 2014.87  5430.1 2020.06  5551.8 2022.06  5612.6 2023.97
#Mann= 4 ,-1 , 0
  4601.2     .07       0  4990.6     .05       0  5012.4     .07       0
    5352    .035       0
Bank Sta=4990.6,5012.4
XS Rating Curve= 0 ,0
Exp/Cntr=0.3,0.1

Type RM Length L Ch R = 1 ,12595   ,280,280,280
BEGIN DESCRIPTION:
Mapping XS 41deb7da
END DESCRIPTION:
XS GIS Cut Line= 2
      1851670.29     13984553.28       1850322.9     13985045.83
#Sta/Elev= 30
    4367 2031.63  4457.8 2028.27  4479.2 2026.32  4574.9  2022.2  4660.1 2012.51
  4702.2  2010.3  4732.7 2007.39    4738 2007.72  4768.6 2016.03  4793.8 2017.21
  4824.3  2020.6  4915.9  2022.8  4971.6  2021.6  4979.5 2019.17  4996.9 2001.91
  5002.2 2002.21  5016.4 1998.32  5016.9 1997.82  5038.3 1998.32  5043.4 2000.23
  5057.9 1999.35  5064.7 2001.16  5075.4 2000.58  5144.2 2002.81  5181.8 2007.76
  5213.8 2009.05  5322.1 2010.73  5543.8 2021.16    5661 2022.67  5801.6 2026.45
#Mann= 3 ,-1 , 0
    4367     .07       0  5016.4     .05       0  5038.3     .07       0
Bank Sta=5016.4,5038.3
XS Rating Curve= 0 ,0
Exp/Cntr=0.3,0.1

Type RM Length L Ch R = 1 ,12315   ,571,571,571
BEGIN DESCRIPTION:
Rough Hallow 25.0
END DESCRIPTION:
XS GIS Cut Line= 3
      1851432.06     13984346.55        1850975.       13984525.
      1850258.36     13984751.05
#Sta/Elev= 30
  4509.6 2031.36  4537.6 2028.75  4613.2 2025.16  4678.2 2022.95  4752.1 2018.13
  4822.3 2008.79  4846.8 2003.41  4852.2 2005.62    4863 2001.74  4871.3 2000.15
  4876.7 2003.52  4906.5 2002.55  4914.4 2000.75  4955.5 2002.08  4966.5 2000.87
  4978.8 2000.32  4979.4 1999.25  4979.9 1998.75    5002 1999.25  5016.4 2000.29
  5042.2 1999.56  5071.9 2001.55  5133.8    2009  5151.1 2008.21  5199.5 2009.35
  5385.3 2015.28  5430.4 2016.37  5524.5 2019.18  5646.9 2019.93  5751.7 2022.01
#Mann= 13 ,-1 , 0
  4509.6    .035       0  4537.6     .07       0  4613.2    .035       0
  4752.1     .07       0    4863    .063       0  4966.5     .07       0
  4979.4     .05       0    5002     .07       0  5071.9     .07       0
  5133.8    .035       0  5385.3      .1       0  5430.4    .063       0
  5646.9     .07       0
Bank Sta=4979.4,5002
XS Rating Curve= 0 ,0
Exp/Cntr=0.3,0.1

Type RM Length L Ch R = 1 ,11744   ,558,558,558
BEGIN DESCRIPTION:
Rough Hallow 24.0
END DESCRIPTION:
XS GIS Cut Line= 3
      1850875.01     13983724.98        1850675.       13984075.
      1850575.01     13984474.96
#Sta/Elev= 30
  4596.9 2043.07  4610.6 2041.91  4654.5 2041.37  4735.1 2037.12  4750.2 2035.44
  4758.2 2036.29  4793.4 2032.61  4815.8 2032.08  4852.5 2029.19  4868.3 2029.39
  4905.7 2026.72  4927.3 2023.39  4933.1 2021.47  4942.4 2016.88  4964.8 2003.54
    4977 1992.41  4980.8 1987.63  4981.3 1987.13  5003.4 1987.63    5031  1993.5
  5072.2  1996.6  5082.5  1996.9  5092.8 1995.33  5100.5 1996.87    5134  1999.7
    5183 2005.24  5278.3 2008.39    5299 2010.01  5353.1 2012.15  5412.3 2013.81
#Mann= 3 ,-1 , 0
  4596.9      .1       0  4980.8     .05       0  5003.4      .1       0
Bank Sta=4980.8,5003.4
XS Rating Curve= 0 ,0
Exp/Cntr=0.3,0.1

Type RM Length L Ch R = 1 ,11186   ,559,559,559
BEGIN DESCRIPTION:
Rough Hallow 23.0
END DESCRIPTION:
XS GIS Cut Line= 3
      1850624.98     13983675.01        1850225.       13983775.
        1850025.       13984125.
#Sta/Elev= 30
  4583.1 2034.35  4642.3 2029.37    4730 2024.38  4758.3 2021.88  4799.5 2016.91
    4815 2012.98  4875.9 2003.06  4923.2 1998.46    4931  1996.4  4943.8 1991.12
  4954.2 1988.57  4978.4 1987.52  4985.1 1988.31  4997.8  1986.9  4998.3  1986.4
  5020.4  1986.9  5024.9 1991.41  5030.7 1991.87  5046.5    1997    5053 1997.68
  5105.5 1998.75  5111.3 1997.76  5121.4 1998.13  5127.1 1997.29  5164.6 2001.16
  5171.2 2001.15  5186.1 2003.21  5245.2 2008.35  5363.2 2015.65  5398.5 2017.09
#Mann= 6 ,-1 , 0
  4583.1      .1       0  4875.9     .07       0  4978.4     .07       0
  4997.8     .05       0  5020.4     .07       0  5171.2      .1       0
Bank Sta=4997.8,5020.4
XS Rating Curve= 0 ,0
Exp/Cntr=0.3,0.1

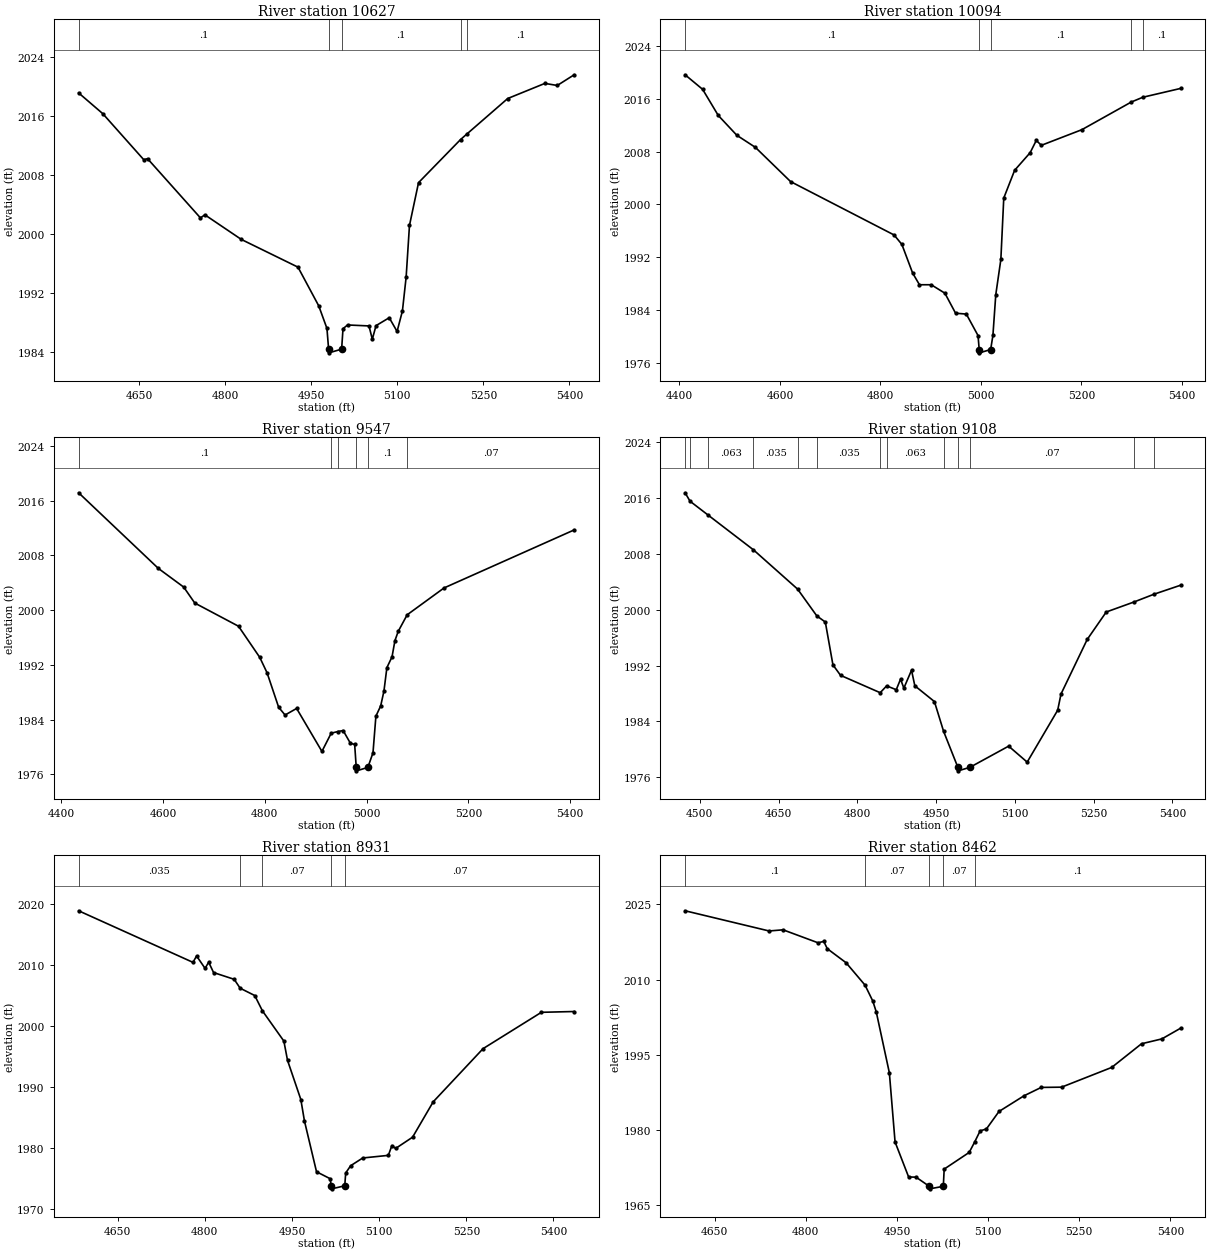
Type RM Length L Ch R = 1 ,10627   ,533,533,533
BEGIN DESCRIPTION:
Rough Hallow 22.0
END DESCRIPTION:
XS GIS Cut Line= 3
      1850124.99     13983175.01        1849775.       13983475.
      1849574.99     13983825.02
#Sta/Elev= 30
  4544.3 2019.08  4586.5 2016.26  4657.9 2010.02  4664.5 2010.16  4756.7 2002.13
  4764.4 2002.55    4828 1999.21  4926.8 1995.45    4963  1990.2  4977.3 1987.14
  4980.2 1984.33  4980.7 1983.83  5002.9 1984.33  5005.3  1987.1  5013.2 1987.61
  5050.6 1987.48  5056.4 1985.68  5062.9 1987.52  5085.9 1988.59  5099.6 1986.73
  5108.9 1989.51  5115.4 1994.11  5121.2 2001.11    5137 2006.91  5210.2 2012.75
  5221.5 2013.52  5292.5 2018.32  5357.3 2020.37  5378.9 2020.09  5408.4 2021.54
#Mann= 5 ,-1 , 0
  4544.3      .1       0  4980.2     .05       0  5002.9      .1       0
  5210.2     .07       0  5221.5      .1       0
Bank Sta=4980.2,5002.9
XS Rating Curve= 0 ,0
Exp/Cntr=0.3,0.1

Type RM Length L Ch R = 1 ,10094   ,547,547,547
BEGIN DESCRIPTION:
Rough Hallow 21.0
END DESCRIPTION:
XS GIS Cut Line= 3
      1849924.96     13982825.02        1849425.       13983125.
      1849224.98     13983475.03
#Sta/Elev= 30
  4411.2 2019.67  4446.1 2017.46  4477.2  2013.5  4514.2 2010.49  4551.1 2008.66
  4621.1 2003.47  4827.1 1995.37  4842.6 1993.94    4864  1989.6  4877.6 1987.82
    4901 1987.82  4928.2 1986.54  4949.5  1983.5  4970.9 1983.37  4994.2 1980.11
  4996.5 1977.99    4997 1977.49  5019.3 1977.99  5023.8 1980.13  5029.5 1986.31
  5039.6 1991.65  5045.4 2000.97    5067 2005.18  5097.9 2007.85  5110.1 2009.71
  5120.2 2008.97  5200.8 2011.34  5299.3 2015.54  5322.1 2016.26  5397.4  2017.6
#Mann= 5 ,-1 , 0
  4411.2      .1       0  4996.5     .05       0  5019.3      .1       0
  5299.3     .07       0  5322.1      .1       0
Bank Sta=4996.5,5019.3
XS Rating Curve= 0 ,0
Exp/Cntr=0.3,0.1

Type RM Length L Ch R = 1 ,9547    ,439,439,439
BEGIN DESCRIPTION:
Rough Hallow 20.0
END DESCRIPTION:
XS GIS Cut Line= 3
      1849625.04     13982324.97        1849175.       13982675.
      1848975.02     13983024.96
#Sta/Elev= 30
  4434.4 2017.16    4591  2006.1  4640.8 2003.37  4662.5 2001.04  4748.4 1997.65
  4790.1  1993.1  4804.5 1990.84  4827.2 1985.81  4839.8 1984.67  4862.5 1985.63
  4912.2 1979.35  4930.4 1982.01  4943.6 1982.26  4953.9  1982.4  4968.3 1980.52
  4976.5 1980.38  4979.6 1977.01  4980.1 1976.51  5002.4 1977.01  5012.5 1979.15
  5018.2  1984.5  5027.6    1986    5034 1988.17  5039.8  1991.6  5049.9 1993.18
  5055.6 1995.55  5062.1 1996.91  5079.6 1999.32  5152.1 2003.25  5407.6 2011.73
#Mann= 6 ,-1 , 0
  4434.4      .1       0  4930.4     .07       0  4943.6      .1       0
  4979.6     .05       0  5002.4      .1       0  5079.6     .07       0
Bank Sta=4979.6,5002.4
XS Rating Curve= 0 ,0
Exp/Cntr=0.3,0.1

Type RM Length L Ch R = 1 ,9108    ,177,177,177
BEGIN DESCRIPTION:
Rough Hallow 19.1
END DESCRIPTION:
XS GIS Cut Line= 2
      1849441.77     13981857.34      1848869.09     13982607.66
#Sta/Elev= 30
  4471.9 2016.76  4481.3 2015.55  4516.3 2013.53  4602.1 2008.58  4686.1 2002.96
  4722.8 1999.11    4739 1998.23  4753.5 1992.09    4768 1990.59  4843.5  1988.1
  4855.8 1989.08  4874.1 1988.53  4882.3 1990.04  4888.6 1988.76  4903.2 1991.32
  4909.5 1989.09  4946.8 1986.83  4964.3 1982.56  4991.5  1977.4    4992  1976.9
  5014.3  1977.4  5088.2 1980.44  5123.5 1978.15  5181.6 1985.59  5187.9 1987.91
  5237.8 1995.73  5274.1 1999.67  5326.4 2001.09  5365.1 2002.22  5415.8 2003.51
#Mann= 13 ,-1 , 0
  4471.9     .07       0  4481.3      .1       0  4516.3    .063       0
  4602.1    .035       0  4686.1    .063       0  4722.8    .035       0
  4843.5      .1       0  4855.8    .063       0  4964.3     .07       0
  4991.5     .05       0  5014.3     .07       0  5326.4     .07       0
  5365.1    .035       0
Bank Sta=4991.5,5014.3
XS Rating Curve= 0 ,0
Exp/Cntr=0.3,0.1

Type RM Length L Ch R = 1 ,8931    ,469,469,469
BEGIN DESCRIPTION:
Rough Hallow 19.0
END DESCRIPTION:
XS GIS Cut Line= 3
      1849280.83     13981796.66      1849031.97     13982130.98
      1848775.25     13982483.42
#Sta/Elev= 30
  4582.8 2018.95  4779.6 2010.49  4785.8 2011.54  4800.4  2009.5  4806.6 2010.52
    4815 2008.82  4850.5 2007.71  4860.8 2006.25  4885.9 2005.05  4899.1 2002.54
    4936 1997.58  4942.3 1994.42  4965.2    1988  4971.4 1984.49  4992.2 1976.15
  5015.3 1975.03  5017.8 1973.85  5018.3 1973.35  5040.8 1973.85  5042.4 1975.95
  5050.9 1977.14  5071.7 1978.41  5115.8 1978.84  5121.9 1980.45  5128.3 1979.97
  5157.5 1981.82    5193 1987.62  5278.8 1996.34  5379.2  2002.3  5435.6 2002.43
#Mann= 5 ,-1 , 0
  4582.8    .035       0  4860.8      .1       0  4899.1     .07       0
  5017.8     .05       0  5040.8     .07       0
Bank Sta=5017.8,5040.8
XS Rating Curve= 0 ,0
Exp/Cntr=0.3,0.1

Type RM Length L Ch R = 1 ,8462    ,564,564,564
BEGIN DESCRIPTION:
Rough Hallow 18.0
END DESCRIPTION:
XS GIS Cut Line= 3
      1848874.98     13981525.03        1848675.       13981875.
        1848575.     13982275.01
#Sta/Elev= 30
  4601.5 2023.72  4739.7 2019.69  4762.7 2019.92  4820.3 2017.33  4829.7 2017.61
  4835.4 2016.16  4866.4 2013.35  4897.6 2008.88  4910.3 2005.72    4916 2003.57
  4937.6 1991.39    4947 1977.58  4969.3  1970.6  4981.5 1970.56  5003.4 1968.73
  5003.9 1968.23  5026.4 1968.73  5027.8 1972.17    5069  1975.5  5078.1 1977.61
    5087  1979.8  5097.3 1980.18    5118 1983.67  5159.2  1986.8  5187.5 1988.47
    5221 1988.52  5303.5 1992.46  5352.5 1997.18    5386 1998.15  5416.9 2000.29
#Mann= 5 ,-1 , 0
  4601.5      .1       0  4897.6     .07       0  5003.4     .05       0
  5026.4     .07       0  5078.1      .1       0
Bank Sta=5003.4,5026.4
XS Rating Curve= 0 ,0
Exp/Cntr=0.3,0.1

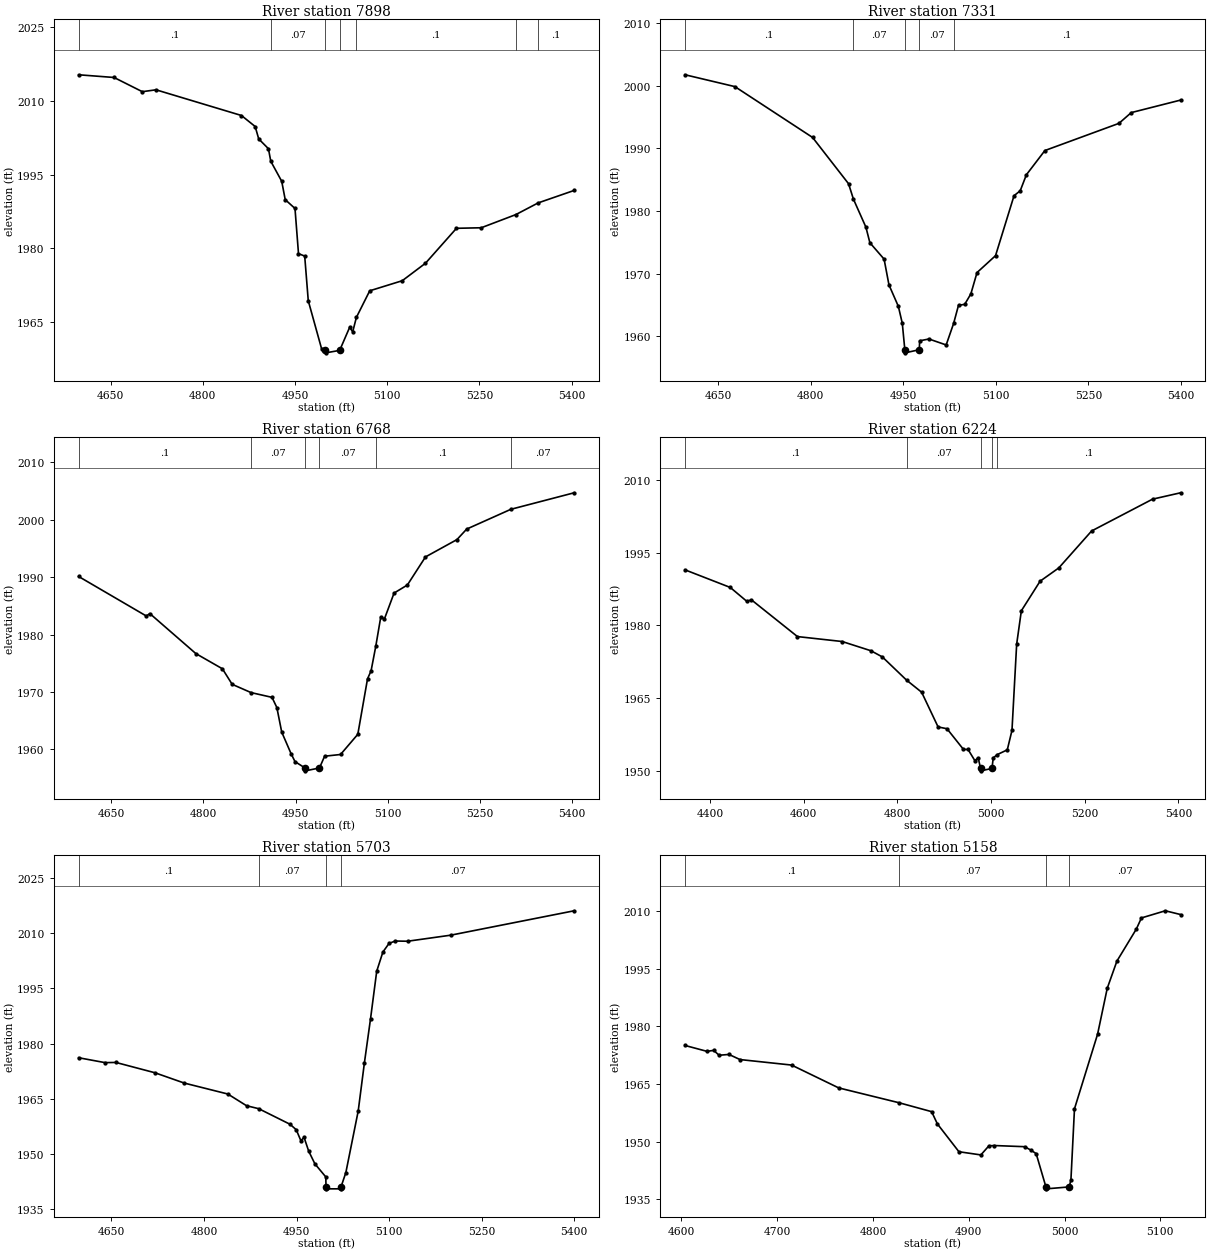
Type RM Length L Ch R = 1 ,7898    ,567,567,567
BEGIN DESCRIPTION:
Rough Hallow 17.0
END DESCRIPTION:
XS GIS Cut Line= 3
      1848524.98     13981475.01        1848175.       13981675.
        1848225.       13982075.
#Sta/Elev= 30
  4597.9 2015.35  4655.5  2014.8  4701.5 2011.91  4723.8 2012.29  4862.8 2007.06
  4885.1 2004.82  4890.9 2002.29  4906.7  2000.3  4910.5 1997.75  4928.3 1993.67
    4934 1989.93  4949.9 1988.14  4955.6 1978.95  4965.7 1978.44  4971.5 1969.35
  4993.1 1959.61  4999.5 1959.25    5000 1958.75  5022.6 1959.25  5038.8 1963.94
  5043.8 1963.04  5049.8 1965.97  5071.5 1971.38  5124.4 1973.43  5162.2 1976.99
  5212.6  1984.1  5252.9 1984.21  5309.2 1986.89  5345.5 1989.27  5404.1 1991.81
#Mann= 7 ,-1 , 0
  4597.9      .1       0  4910.5     .07       0  4999.5     .05       0
  5022.6     .07       0  5049.8      .1       0  5309.2     .07       0
  5345.5      .1       0
Bank Sta=4999.5,5022.6
XS Rating Curve= 0 ,0
Exp/Cntr=0.3,0.1

Type RM Length L Ch R = 1 ,7331    ,563,563,563
BEGIN DESCRIPTION:
Rough Hallow 16.0
END DESCRIPTION:
XS GIS Cut Line= 3
      1847825.02     13981274.97        1847625.       13981625.
        1847625.     13982024.95
#Sta/Elev= 30
  4596.5 2001.76  4677.2 1999.87  4803.1 1991.75  4861.4 1984.36  4869.3  1981.9
  4889.5 1977.43    4896 1974.93    4919 1972.32  4926.9  1968.2  4942.1 1964.78
  4948.5 1962.07  4952.6 1957.85  4953.1 1957.35  4976.1 1957.85  4976.6 1959.27
  4991.7 1959.56  5019.6 1958.61  5031.7 1962.05  5039.6 1964.95  5049.6 1965.09
  5059.6 1966.76  5069.6 1970.17  5099.6 1972.87  5129.6 1982.45  5139.6 1983.23
  5149.6 1985.79  5179.6 1989.66  5299.6    1994  5319.6 1995.72  5399.6 1997.72
#Mann= 5 ,-1 , 0
  4596.5      .1       0  4869.3     .07       0  4952.6     .05       0
  4976.1     .07       0  5031.7      .1       0
Bank Sta=4952.6,4976.1
XS Rating Curve= 0 ,0
Exp/Cntr=0.3,0.1

Type RM Length L Ch R = 1 ,6768    ,544,544,544
BEGIN DESCRIPTION:
Rough Hallow 15.0
END DESCRIPTION:
XS GIS Cut Line= 3
      1847324.99     13981175.01        1847125.       13981525.
      1846925.01     13981874.99
#Sta/Elev= 30
    4597 1990.13  4707.1 1983.24  4712.9 1983.66  4787.7 1976.69  4830.9 1974.04
  4846.8 1971.33  4877.5 1969.89  4911.6 1969.06  4919.5 1967.28  4927.4 1963.01
  4942.5 1959.27    4949 1957.86  4965.3 1956.75  4965.8 1956.25  4988.8 1956.75
  4997.2  1958.8  5023.1  1959.1  5051.2 1962.62    5067 1972.29  5072.8 1973.69
  5080.4 1977.95  5088.6 1983.11  5094.4  1982.7  5110.2 1987.24  5131.8 1988.64
  5161.3 1993.54  5212.5 1996.56  5228.3 1998.39  5300.2 2001.84  5403.2 2004.72
#Mann= 6 ,-1 , 0
    4597      .1       0  4877.5     .07       0  4965.3     .05       0
  4988.8     .07       0  5080.4      .1       0  5300.2     .07       0
Bank Sta=4965.3,4988.8
XS Rating Curve= 0 ,0
Exp/Cntr=0.3,0.1

Type RM Length L Ch R = 1 ,6224    ,521,521,521
BEGIN DESCRIPTION:
Rough Hallow 14.0
END DESCRIPTION:
XS GIS Cut Line= 3
      1847286.76     13981083.43        1846675.       13981325.
      1846275.03       13981325.
#Sta/Elev= 30
  4346.9 1991.46  4443.3 1987.83  4478.4 1984.98  4488.6 1985.26  4586.7 1977.68
  4682.1 1976.66  4743.6 1974.75    4768 1973.47  4819.6 1968.68  4851.8 1966.18
  4886.9 1959.01  4905.9 1958.64    4941 1954.37  4950.9 1954.35  4965.4 1952.04
  4972.4 1952.65  4977.6 1950.44  4978.1 1949.94  5001.9 1950.44  5004.6 1952.61
  5013.1 1953.29  5034.6 1954.28  5044.6  1958.3  5054.6 1976.11  5064.6 1983.01
  5104.6 1989.12  5144.6 1991.87  5214.6  1999.5  5344.6 2006.07  5404.6 2007.39
#Mann= 5 ,-1 , 0
  4346.9      .1       0  4819.6     .07       0  4977.6     .05       0
  5001.9     .07       0  5013.1      .1       0
Bank Sta=4977.6,5001.9
XS Rating Curve= 0 ,0
Exp/Cntr=0.3,0.1

Type RM Length L Ch R = 1 ,5703    ,545,545,545
BEGIN DESCRIPTION:
Rough Hallow 13.0
END DESCRIPTION:
XS GIS Cut Line= 3
      1846924.97       13980825.        1846525.       13980875.
      1846124.98       13980875.
#Sta/Elev= 30
  4596.9 1976.16  4639.7 1974.83  4657.3 1974.88  4720.3 1972.09  4768.2 1969.27
  4838.7  1966.3    4869 1963.12  4888.8 1962.31  4939.5 1958.08  4949.6 1956.59
  4957.1  1953.6  4962.2 1954.54  4969.7  1950.8  4979.8 1947.32  4997.5 1943.76
  4997.8 1941.03  4998.3 1940.53  5021.6 1940.53  5022.1 1941.03    5030 1944.97
    5050 1961.68    5060 1974.72    5070 1986.79    5080 1999.68    5090 2004.89
    5100 2007.24    5110 2007.88    5130 2007.82    5200 2009.47    5400  2016.1
#Mann= 4 ,-1 , 0
  4596.9      .1       0  4888.8     .07       0  4997.8     .05       0
  5022.1     .07       0
Bank Sta=4997.8,5022.1
XS Rating Curve= 0 ,0
Exp/Cntr=0.3,0.1

Type RM Length L Ch R = 1 ,5158    ,486,486,486
BEGIN DESCRIPTION:
Rough Hallow 12.0
END DESCRIPTION:
XS GIS Cut Line= 3
      1847025.03     13980575.02        1846675.     13980381.07
       1846559.2     13980364.14
#Sta/Elev= 30
    4604 1975.03  4626.9  1973.5  4633.8 1973.76  4639.5 1972.49  4649.8  1972.7
  4661.3 1971.37  4715.1 1969.94  4764.3    1964  4827.6 1960.12  4861.3 1957.82
  4867.3 1954.64  4889.8  1947.4  4912.7 1946.57  4921.1 1948.94  4926.9 1949.01
  4958.4 1948.71  4964.6 1947.86  4970.4 1946.91  4980.6 1938.25  4981.1 1937.75
  5004.9 1938.25  5006.7 1940.09  5010.4 1958.56  5034.5 1977.95  5044.6 1989.91
  5054.7 1996.98  5074.9 2005.28  5080.3  2008.2  5105.2 2010.06  5121.2 2009.08
#Mann= 4 ,-1 , 0
    4604      .1       0  4827.6     .07       0  4980.6     .05       0
  5004.9     .07       0
Bank Sta=4980.6,5004.9
XS Rating Curve= 0 ,0
Exp/Cntr=0.3,0.1

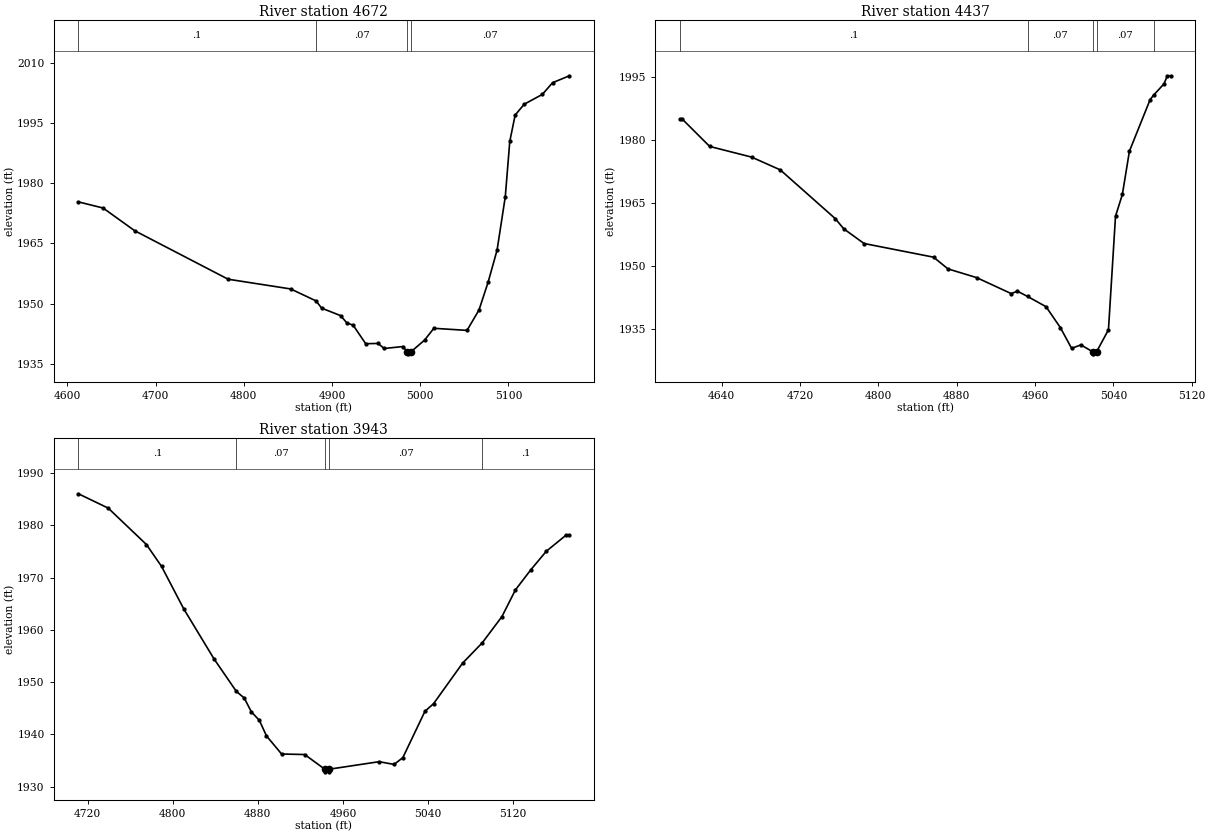
Type RM Length L Ch R = 1 ,4672    ,235,235,235
BEGIN DESCRIPTION:
Rough Hallow 11.0
END DESCRIPTION:
XS GIS Cut Line= 3
      1847324.98     13980324.98      1847039.36     13980061.82
      1846875.01       13980025.
#Sta/Elev= 30
  4612.4 1975.35  4640.4 1973.82  4676.2 1968.17  4782.2 1956.09  4853.1 1953.67
  4881.8  1950.7  4888.3 1948.88  4909.8 1947.02  4916.6 1945.26    4924 1944.63
  4938.2 1940.03  4952.3  1940.1  4959.1 1938.84  4980.1 1939.32  4985.5 1938.01
  4985.8 1937.51  4989.5 1938.01  5004.9 1940.92  5015.5 1943.87  5053.1 1943.35
  5066.7 1948.44    5077 1955.33  5087.2 1963.35  5096.5 1976.64  5101.6 1990.43
  5107.7 1996.98    5118 1999.67  5138.5 2002.11  5150.1 2005.02  5169.2 2006.75
#Mann= 4 ,-1 , 0
  4612.4      .1       0  4881.8     .07       0  4985.5     .05       0
  4989.5     .07       0
Bank Sta=4985.5,4989.5
XS Rating Curve= 0 ,0
Exp/Cntr=0.3,0.1

Type RM Length L Ch R = 1 ,4437    ,494,494,494
BEGIN DESCRIPTION:
Rough Hallow 10.0
END DESCRIPTION:
XS GIS Cut Line= 3
      1847483.11     13980269.42      1847243.72     13979945.81
      1847175.01     13979875.01
#Sta/Elev= 30
  4597.5 1984.86  4600.1 1984.86  4627.9  1978.4  4670.7 1975.86    4700 1972.82
  4756.3 1961.19  4764.7 1958.82  4785.5 1955.31  4856.5 1952.06  4871.1 1949.28
  4900.4  1947.2  4935.8 1943.39    4942 1943.98  4952.4 1942.72  4971.3 1940.28
  4985.9 1935.31  4997.4 1930.37  5006.8  1931.2  5018.9 1929.57  5019.2 1929.07
  5022.9 1929.57    5035 1934.79  5042.2  1961.8  5049.2 1966.98  5056.4 1977.27
  5077.5 1989.51    5081 1990.57  5091.6 1993.26  5095.2  1995.2  5098.7  1995.2
#Mann= 5 ,-1 , 0
  4597.5      .1       0  4952.4     .07       0  5018.9     .05       0
  5022.9     .07       0    5081      .1       0
Bank Sta=5018.9,5022.9
XS Rating Curve= 0 ,0
Exp/Cntr=0.3,0.1

Type RM Length L Ch R = 1 ,3943    ,489,489,489
BEGIN DESCRIPTION:
Rough Hallow 9.0
END DESCRIPTION:
XS GIS Cut Line= 3
        1847875.       13979875.      1847661.28     13979681.32
      1847524.98     13979574.98
#Sta/Elev= 30
  4711.4 1986.03  4739.4 1983.29  4775.3 1976.33  4789.5 1972.15  4810.4 1964.01
  4838.8 1954.46  4859.8 1948.24  4867.2 1946.98  4873.9 1944.32  4881.4 1942.71
  4888.1 1939.73  4902.3 1936.27    4924 1936.17  4942.9 1933.36  4943.1 1932.86
  4946.6 1932.86  4946.9 1933.36  4993.9  1934.8    5008 1934.28  5016.2 1935.57
    5037 1944.44  5045.1  1945.9  5072.3 1953.63  5090.9 1957.55  5109.3 1962.54
    5122 1967.65  5136.5 1971.51    5151 1975.04  5169.5 1978.11  5172.7 1978.11
#Mann= 5 ,-1 , 0
  4711.4      .1       0  4859.8     .07       0  4942.9     .05       0
  4946.9     .07       0  5090.9      .1       0
Bank Sta=4942.9,4946.9
XS Rating Curve= 0 ,0
Exp/Cntr=0.3,0.1