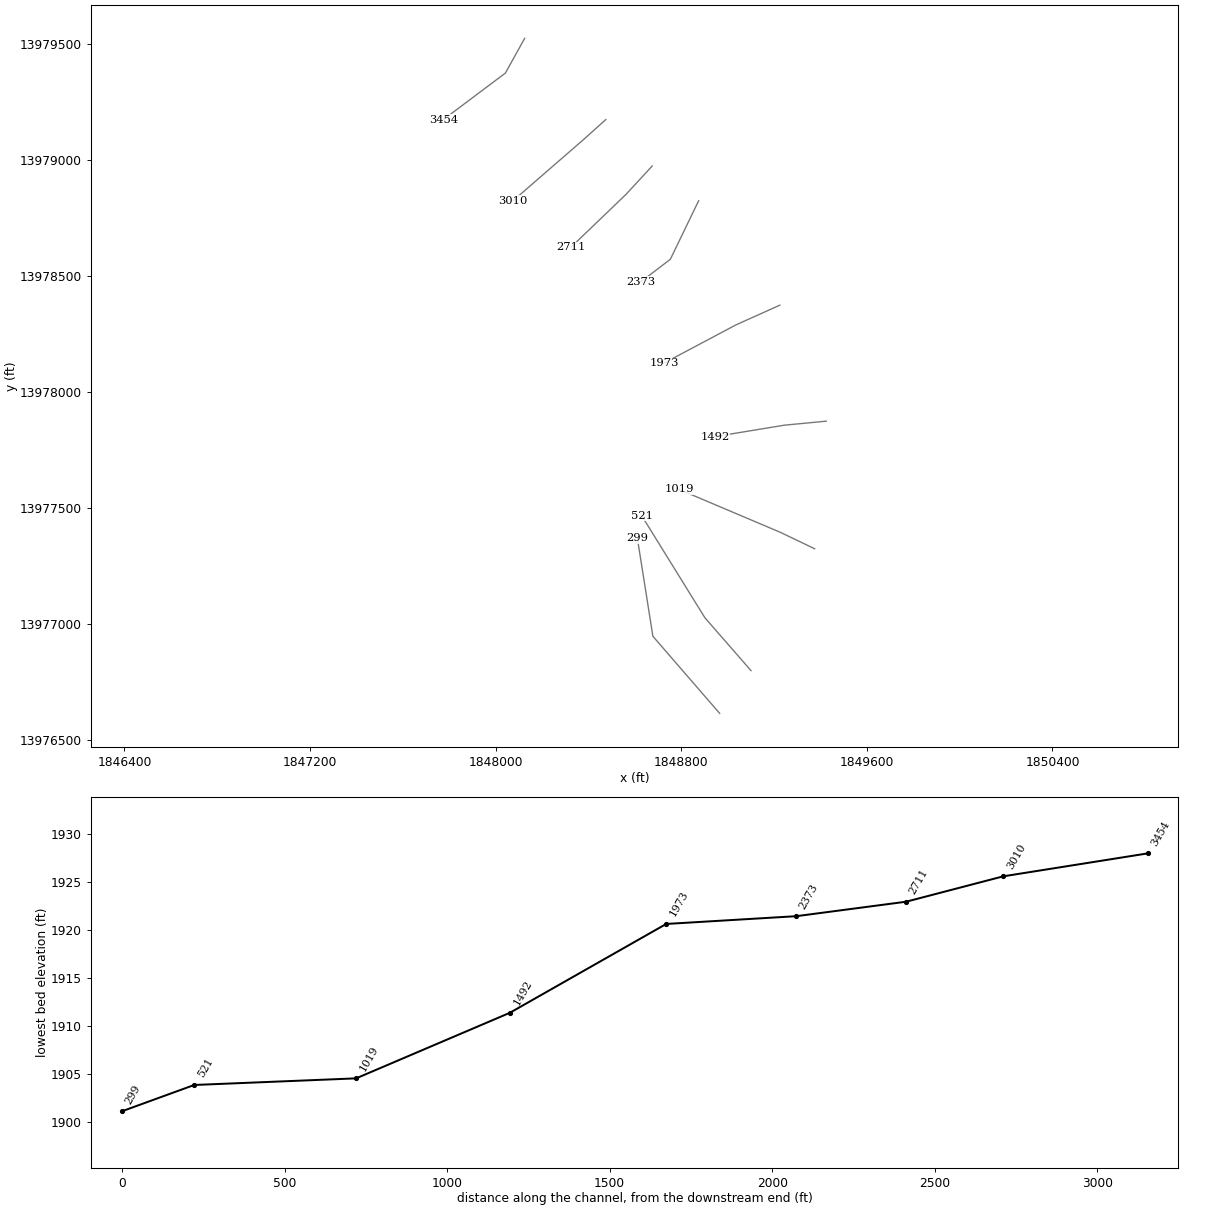
HEC-RAS study Rough Hollow.prj: Rough Hollow Base Level Engineering

--- Rough Hollow.g01 (geometry) --- (continued)

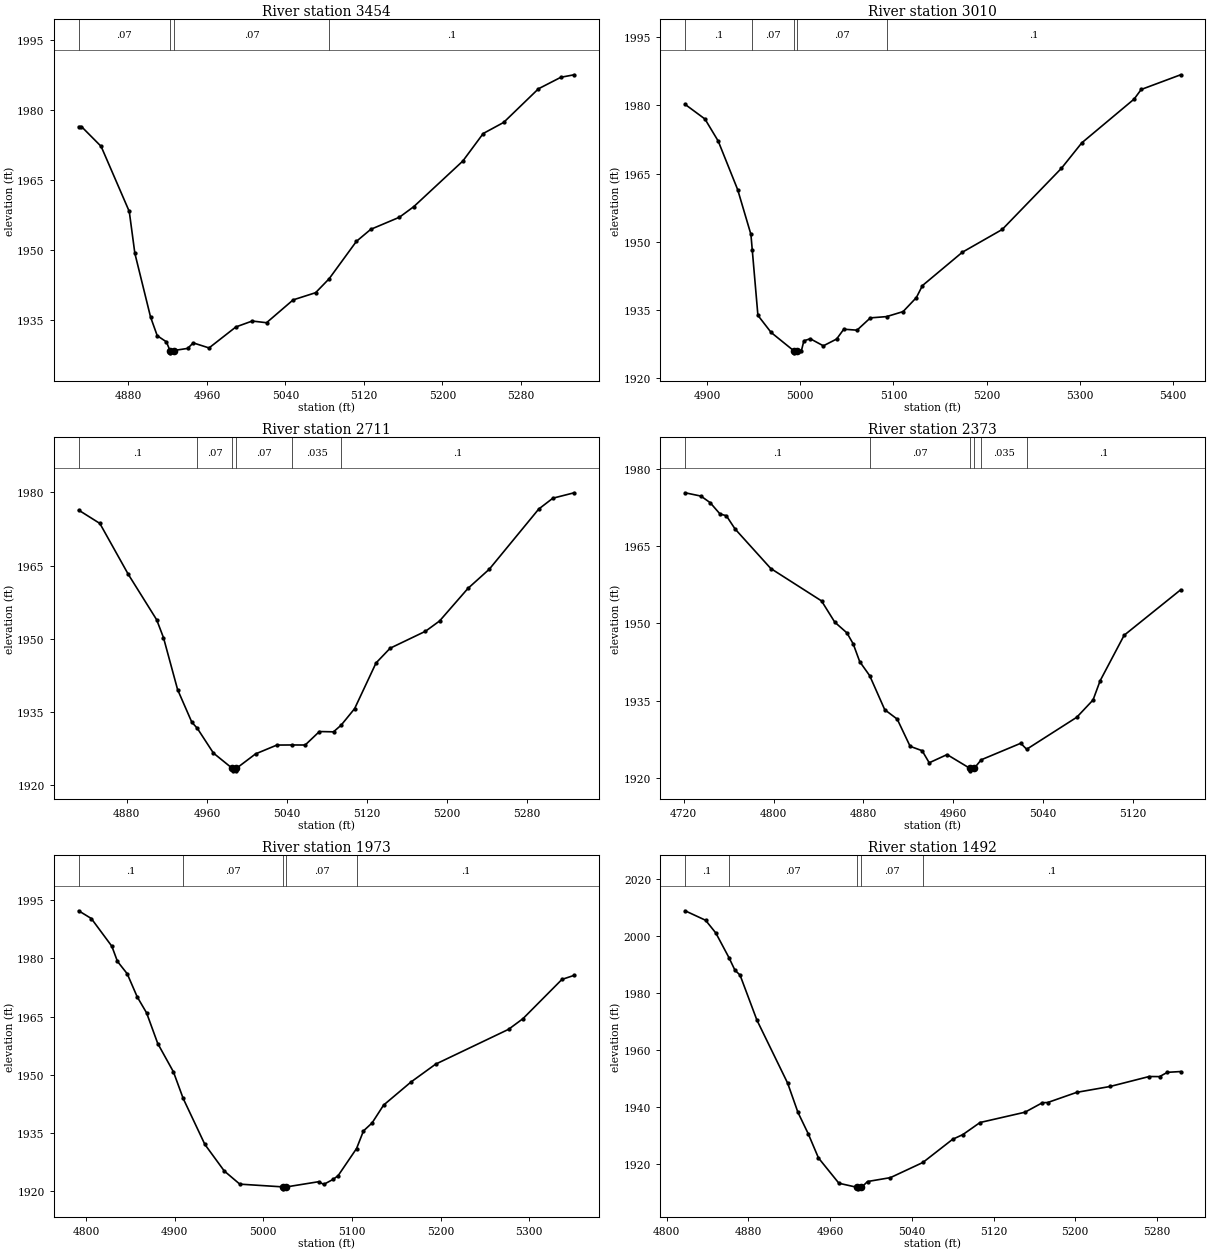
Type RM Length L Ch R = 1 ,3454    ,444,444,444
BEGIN DESCRIPTION:
Rough Hallow 8.0
END DESCRIPTION:
XS GIS Cut Line= 3
      1848125.02     13979525.03       1848042.2     13979375.46
      1847775.01       13979175.
#Sta/Elev= 30
  4829.3 1976.44  4832.2 1976.44  4852.2 1972.21  4880.9 1958.27  4886.6  1949.3
  4902.6 1935.66  4909.4 1931.66  4918.7 1930.35  4922.4 1928.49  4922.6 1927.99
  4926.4 1928.49  4940.4 1928.94  4946.1 1930.12  4962.2 1929.04  4989.6 1933.54
  5006.2  1934.8  5020.8 1934.44  5047.9 1939.33  5070.8 1940.87  5084.6 1943.86
  5112.4 1951.87    5127 1954.44  5156.2 1957.03  5170.8 1959.29  5220.8 1969.06
  5241.6 1974.96  5262.4 1977.33  5297.9 1984.54  5320.8 1987.01  5334.3 1987.54
#Mann= 4 ,-1 , 0
  4829.3     .07       0  4922.4     .05       0  4926.4     .07       0
  5084.6      .1       0
Bank Sta=4922.4,4926.4
XS Rating Curve= 0 ,0
Exp/Cntr=0.3,0.1

Type RM Length L Ch R = 1 ,3010    ,299,299,299
BEGIN DESCRIPTION:
Rough Hallow 7.0
END DESCRIPTION:
XS GIS Cut Line= 3
      1848474.97     13979174.97      1848383.98     13979093.24
      1848074.98     13978824.98
#Sta/Elev= 30
  4876.6 1980.19  4897.9 1976.97  4912.1 1972.13    4933 1961.45  4947.2 1951.62
  4948.6  1948.3  4954.7 1933.83  4968.9 1930.07  4992.9  1926.1  4993.1  1925.6
  4996.9  1926.1  5001.4  1926.1    5004 1928.24  5010.8  1928.7  5024.9 1927.14
  5039.1 1928.63  5046.8 1930.79    5061 1930.58  5075.3 1933.28  5092.7 1933.56
  5110.4 1934.66  5124.6 1937.73  5131.2 1940.38    5174 1947.71  5216.7  1952.7
  5280.3 1966.16  5302.1 1971.74  5358.2 1981.35  5365.8 1983.46  5408.1 1986.69
#Mann= 5 ,-1 , 0
  4876.6      .1       0  4948.6     .07       0  4992.9     .05       0
  4996.9     .07       0  5092.7      .1       0
Bank Sta=4992.9,4996.9
XS Rating Curve= 0 ,0
Exp/Cntr=0.3,0.1

Type RM Length L Ch R = 1 ,2711    ,338,338,338
BEGIN DESCRIPTION:
Rough Hallow 6.0
END DESCRIPTION:
XS GIS Cut Line= 3
      1848674.99     13978974.99       1848560.8     13978851.36
      1848324.97     13978624.97
#Sta/Elev= 30
  4831.8 1976.36    4853 1973.63  4881.4 1963.21  4909.8 1953.89  4916.6 1950.23
  4930.7 1939.59  4944.9 1932.92  4950.4 1931.66  4966.5 1926.59  4985.4 1923.45
  4985.7 1922.95  4989.2 1922.95  4989.4 1923.45  5008.6 1926.42  5029.9 1928.23
  5045.2 1928.25  5058.2 1928.24  5072.4    1931  5086.5 1930.94  5094.1  1932.3
  5107.6 1935.69    5129 1945.05  5143.1 1948.07  5178.4 1951.54  5192.5 1953.65
  5220.8 1960.31  5242.2 1964.26  5291.6 1976.58  5305.7  1978.8    5327 1979.91
#Mann= 6 ,-1 , 0
  4831.8      .1       0  4950.4     .07       0  4985.4     .05       0
  4989.4     .07       0  5045.2    .035       0  5094.1      .1       0
Bank Sta=4985.4,4989.4
XS Rating Curve= 0 ,0
Exp/Cntr=0.3,0.1

Type RM Length L Ch R = 1 ,2373    ,400,400,400
BEGIN DESCRIPTION:
Rough Hallow 5.0
END DESCRIPTION:
XS GIS Cut Line= 3
      1848875.02     13978825.03      1848752.99     13978572.72
        1848625.       13978475.
#Sta/Elev= 30
  4721.2 1975.31  4735.3 1974.67  4743.5  1973.4  4752.3  1971.2  4757.9 1970.87
  4765.7  1968.3  4797.5 1960.64  4842.7 1954.36  4854.5 1950.24  4865.3 1948.17
  4870.9 1946.04  4876.7  1942.6  4885.6 1939.87    4899 1933.28  4910.1 1931.46
  4921.6 1926.19  4932.3 1925.34  4938.6    1923  4954.5 1924.59  4974.7 1921.94
    4975 1921.44  4978.7 1921.94  4984.9 1923.58  5020.1 1926.78  5025.4 1925.62
    5070 1931.82  5084.5 1935.17  5090.8 1938.89  5112.2 1947.71  5162.5 1956.51
#Mann= 6 ,-1 , 0
  4721.2      .1       0  4885.6     .07       0  4974.7     .05       0
  4978.7     .07       0  4984.9    .035       0  5025.4      .1       0
Bank Sta=4974.7,4978.7
XS Rating Curve= 0 ,0
Exp/Cntr=0.3,0.1

Type RM Length L Ch R = 1 ,1973    ,481,481,481
BEGIN DESCRIPTION:
Rough Hallow 4.0
END DESCRIPTION:
XS GIS Cut Line= 3
      1849224.98     13978374.99      1849036.24      13978290.2
      1848724.98     13978124.99
#Sta/Elev= 30
  4791.5 1992.25  4805.8 1990.26    4829 1983.11  4835.3 1979.22  4846.3 1976.04
  4857.6 1970.08  4868.2 1965.95  4880.8 1958.06  4898.5 1950.76  4909.5 1943.91
    4934 1932.06  4955.9 1925.22  4973.4 1921.84  5022.1 1921.13  5022.4 1920.63
  5026.1 1921.13  5062.5 1922.47  5068.1 1921.77  5078.8 1923.08  5084.4 1924.03
  5105.2 1931.02    5113 1935.55  5122.7  1937.6  5135.7  1942.2  5166.7 1948.16
  5194.4 1952.74  5276.7 1961.71    5293 1964.46    5337 1974.57  5350.8 1975.62
#Mann= 5 ,-1 , 0
  4791.5      .1       0  4909.5     .07       0  5022.1     .05       0
  5026.1     .07       0  5105.2      .1       0
Bank Sta=5022.1,5026.1
XS Rating Curve= 0 ,0
Exp/Cntr=0.3,0.1

Type RM Length L Ch R = 1 ,1492    ,473,473,473
BEGIN DESCRIPTION:
Rough Hallow 3.0
END DESCRIPTION:
XS GIS Cut Line= 3
      1849424.96       13977875.      1849244.39     13977857.72
      1848944.63     13977808.31
#Sta/Elev= 30
    4818 2008.75  4838.1 2005.42  4848.1 2000.96  4860.9 1992.37  4866.8 1987.94
  4871.8 1986.23  4888.3 1970.47  4918.4 1948.38  4928.5 1938.14  4938.5  1930.7
  4948.6 1922.17  4968.6 1913.32  4986.7 1911.86    4987 1911.36  4990.7 1911.86
  4996.6 1913.92    5019 1915.28  5050.8 1920.59  5079.9  1928.7    5090 1930.37
  5106.8 1934.59  5150.8  1938.2  5167.9 1941.53    5173 1941.59  5201.5 1945.16
  5234.1 1947.21  5272.4  1950.7  5282.6 1950.67  5290.2 1952.17  5303.2 1952.44
#Mann= 5 ,-1 , 0
    4818      .1       0  4860.9     .07       0  4986.7     .05       0
  4990.7     .07       0  5050.8      .1       0
Bank Sta=4986.7,4990.7
XS Rating Curve= 0 ,0
Exp/Cntr=0.3,0.1

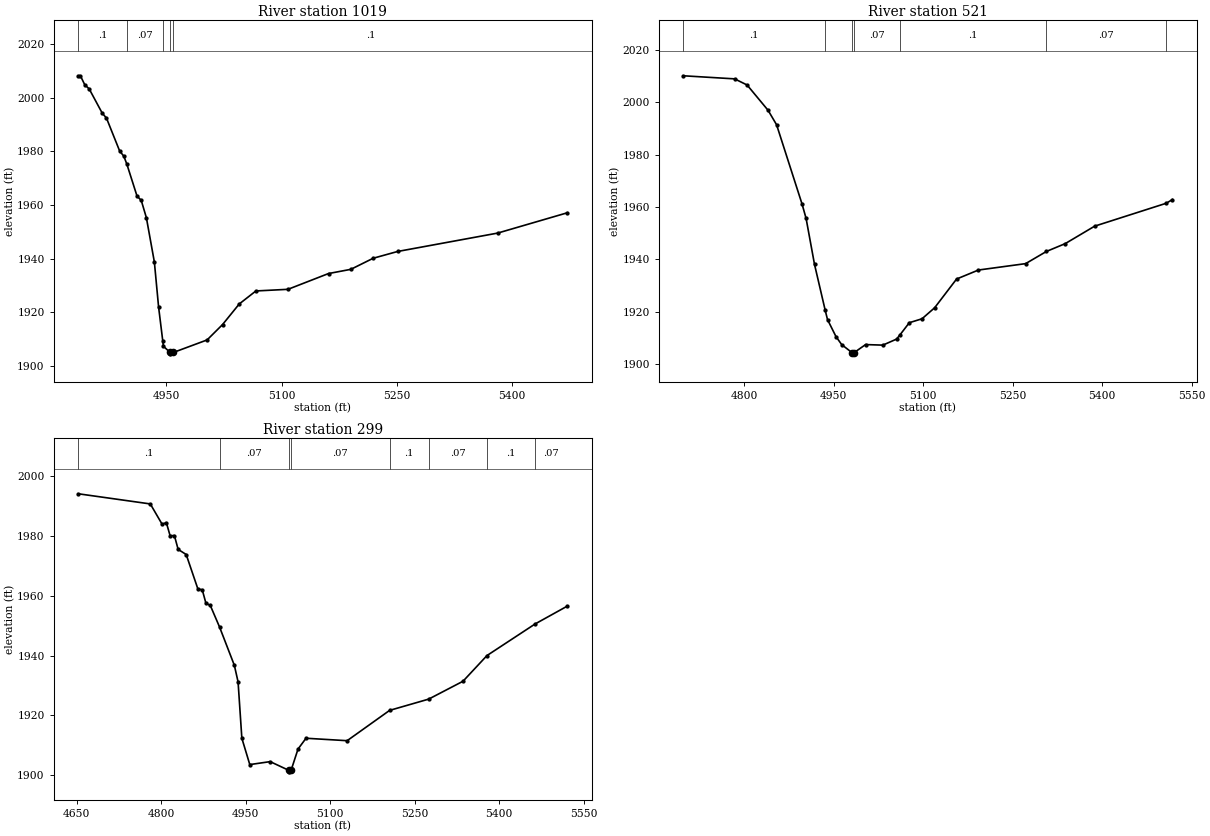
Type RM Length L Ch R = 1 ,1019    ,498,498,498
BEGIN DESCRIPTION:
Rough Hallow 2.0
END DESCRIPTION:
XS GIS Cut Line= 3
      1849374.96     13977325.02      1849227.25     13977395.91
      1848791.27     13977580.54
#Sta/Elev= 30
  4835.1 2008.17  4837.8 2008.17  4843.6 2004.77  4849.2 2003.32  4866.3 1994.22
  4871.8  1992.4  4888.9 1980.18  4894.4 1978.18  4898.3 1975.28  4911.6 1963.33
  4917.1 1961.73  4923.8 1955.26  4934.2 1938.76  4939.7    1922  4945.2  1909.2
    4946 1907.34  4954.8 1905.02  4955.1 1904.52  4958.8 1905.02  5002.9  1909.7
  5023.1 1915.45  5044.8 1923.11  5066.5 1927.96  5108.3 1928.57  5161.1 1934.45
  5190.2 1936.02  5219.3 1940.15  5251.2 1942.68  5381.5 1949.53  5472.4 1957.11
#Mann= 5 ,-1 , 0
  4835.1      .1       0  4898.3     .07       0  4945.2      .1       0
  4954.8     .05       0  4958.8      .1       0
Bank Sta=4954.8,4958.8
XS Rating Curve= 0 ,0
Exp/Cntr=0.3,0.1

Type RM Length L Ch R = 1 ,521     ,222,222,222
BEGIN DESCRIPTION:
Rough Hallow 1.0
END DESCRIPTION:
XS GIS Cut Line= 3
      1849100.64     13976799.84      1848901.81      13977027.9
      1848629.48     13977467.76
#Sta/Elev= 30
  4697.9 2010.11  4783.9 2008.93  4804.8 2006.58  4839.9 1996.93  4854.2 1991.39
  4896.9 1961.09  4903.7 1955.56  4917.8    1938  4935.7 1920.48  4939.6 1916.91
  4953.9 1910.37  4963.4 1907.35  4980.4 1904.33  4980.6 1903.83  4984.4 1904.33
  5003.4 1907.37  5032.3 1907.16  5055.4 1909.47  5060.9 1911.04  5076.7 1915.73
    5098 1917.23  5119.2 1921.45  5155.9 1932.42  5192.5 1935.86  5271.7 1938.31
  5306.5 1942.96  5338.1 1945.96  5387.4 1952.63  5507.3 1961.38  5517.8  1962.8
#Mann= 7 ,-1 , 0
  4697.9      .1       0  4935.7     .07       0  4980.4     .05       0
  4984.4     .07       0  5060.9      .1       0  5306.5     .07       0
  5507.3      .1       0
Bank Sta=4980.4,4984.4
XS Rating Curve= 0 ,0
Exp/Cntr=0.3,0.1

Type RM Length L Ch R = 1 ,299     ,0,0,0
BEGIN DESCRIPTION:
Rough Hallow 0.0
END DESCRIPTION:
XS GIS Cut Line= 3
      1848965.61     13976615.59      1848677.76     13976947.95
      1848610.75     13977371.19
#Sta/Elev= 30
  4652.8 1994.21  4780.6 1990.81  4801.5 1984.03  4809.1 1984.54  4815.7 1980.19
  4823.4  1980.2    4830 1975.59  4844.3 1973.87  4865.1 1962.31  4872.8 1962.06
  4879.4 1957.51    4887 1956.85  4903.5  1949.6  4929.8 1936.76  4936.4 1931.22
  4943.1 1912.34  4957.2 1903.52  4993.4 1904.51  5026.5 1901.59  5026.8 1901.09
  5030.5 1901.59  5042.8 1908.72    5057 1912.34    5130 1911.52  5205.4 1921.67
  5274.7 1925.44  5335.7 1931.43  5378.2 1940.03  5463.8 1950.63    5521 1956.61
#Mann= 8 ,-1 , 0
  4652.8      .1       0  4903.5     .07       0  5026.5     .05       0
  5030.5     .07       0  5205.4      .1       0  5274.7     .07       0
  5378.2      .1       0  5463.8     .07       0
Bank Sta=5026.5,5030.5
XS Rating Curve= 0 ,0
Exp/Cntr=0.3,0.1

Chan Stop Cuts=-1
Use User Specified Reach Order=0
Composite Channel Slope=5