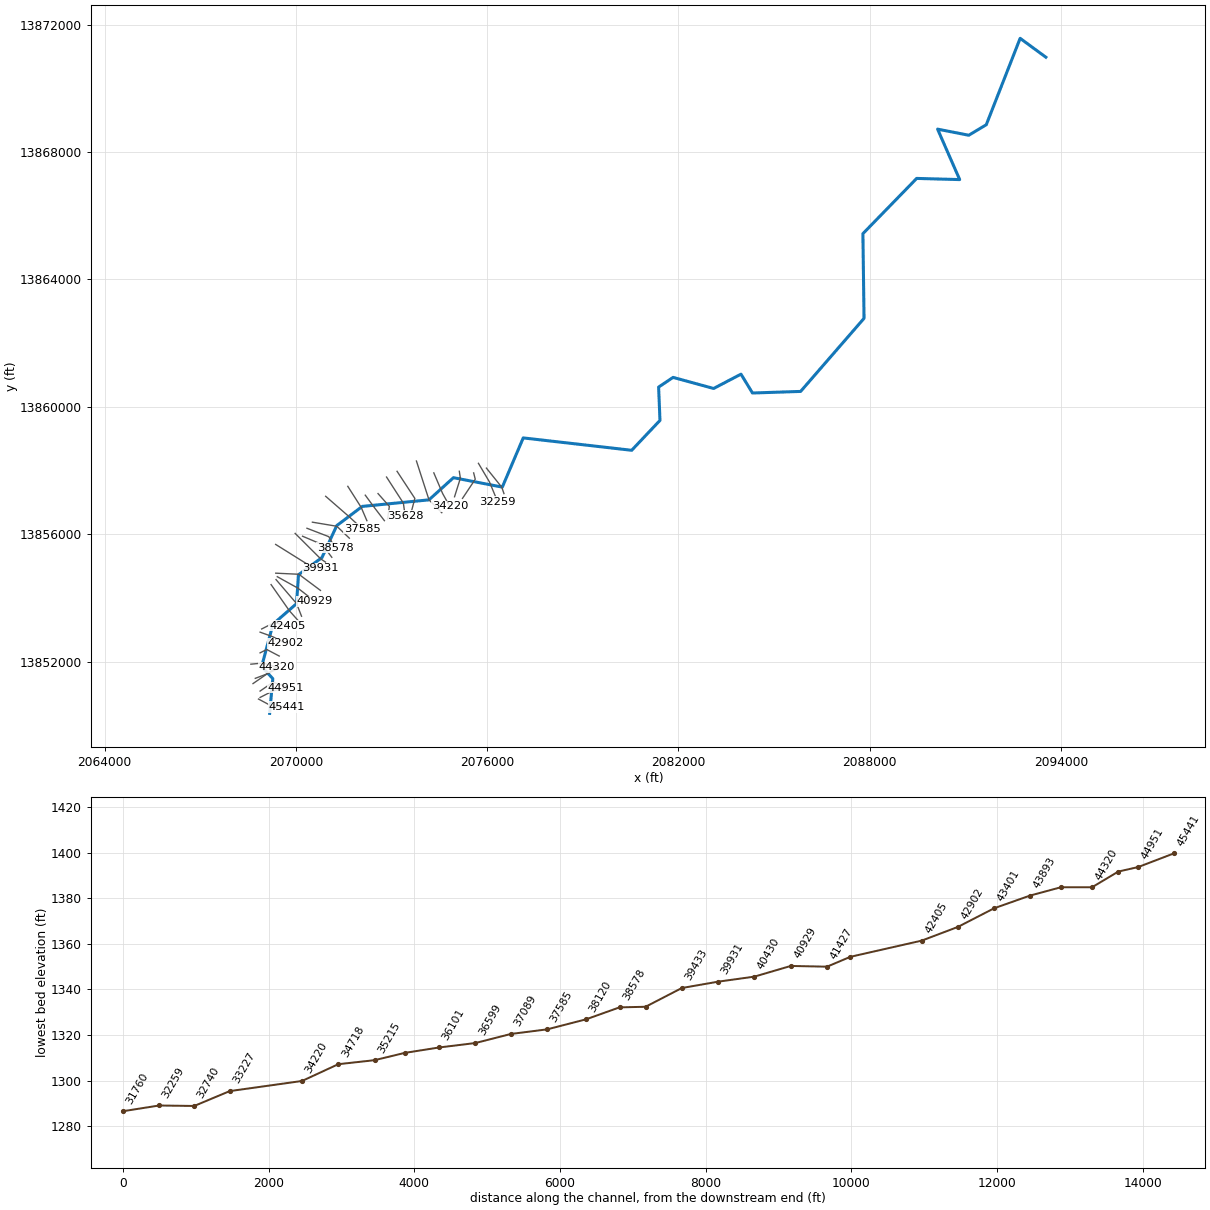
--- SPRING CREEK.prj (project) ---

Proj Title=SPRING CREEK Base Level Engineering
Current Plan=p01
Default Exp/Contr=0.3,0.1
English Units
Geom File=g01
Flow File=f01
Plan File=p01
Y Axis Title=Elevation
X Axis Title(PF)=Main Channel Distance
X Axis Title(XS)=Station
BEGIN DESCRIPTION:
SPRING CREEK
END DESCRIPTION:
DSS Export Rating Curves= 0
DSS Export Rating Curve Sorted= 0
DSS Export Volume Flow Curves= 0
DXF OffsetX= 0
DXF OffsetY= 0
DXF ScaleX= 1
DXF ScaleY= 10

--- SPRING CREEK.p01 (plan) ---

Plan Title=Multiple Run
Short Identifier=Multiple
Geom File=g01
Flow File=f01
Subcritical Flow
K Sum by GR= 0
Std Step Tol= 0.01
Critical Tol= 0.01
Num of Std Step Trials= 20
Max Error Tol= 0.3
Flow Tol Ratio= 0.001
Split Flow NTrial= 30
Split Flow Tol= 0.02
Split Flow Ratio= 0.02
Log Output Level= 0
Friction Slope Method= 1
Unsteady Friction Slope Method= 2
Unsteady Bridges Friction Slope Method= 1
Parabolic Critical Depth
Global Vel Dist=  1 , 1 , 1
Global Log Level= 0
CheckData=True
Encroach Param= -1, 0, 0, 0
BEGIN DESCRIPTION:
Multiple Run
END DESCRIPTION:

--- SPRING CREEK.f01 (steady flow) ---

Flow Title=Multiple
Program Version=4.10
Number of Profiles= 7
Profile Names=10-year,25-year,50-year,1pct_min,100-year,1pct_plu,500-year
River Rch & RM=SPRING CREEK,Reach-1         ,45441
    1694    2929    4130    2821    5629   11232   10335
River Rch & RM=SPRING CREEK,Reach-1         ,41427
    3834    6875    9929    6924   13815   27565   26462
River Rch & RM=SPRING CREEK,Reach-1         ,37089
    3883    6971   10072    7024   14014   27962   26858
River Rch & RM=SPRING CREEK,Reach-1         ,33227
    4177    7505   10852    7570   15105   30137   28967
River Rch & RM=SPRING CREEK,Reach-1         ,29788
    4439    7988   11561    8070   16102   32127   30921
River Rch & RM=SPRING CREEK,Reach-1         ,27834
    6256   11411   16667   11730   23404   46698   45688
River Rch & RM=SPRING CREEK,Reach-1         ,22429
    6552   11956   17467   12294   24529   48941   47887
River Rch & RM=SPRING CREEK,Reach-1         ,18800
    6577   12001   17532   12339   24620   49122   48060
River Rch & RM=SPRING CREEK,Reach-1         ,17771
    8288   15237   22372   15816   31557   62964   62150
River Rch & RM=SPRING CREEK,Reach-1         ,14020
    8836   16220   23791   16795   33511   66863   65808
River Rch & RM=SPRING CREEK,Reach-1         ,4567
    9007   16524   24227   17094   34106   68051   66902
River Rch & RM=SPRING CREEK,Reach-1         ,1098
    9102   16748   24600   17387   34692   69220   68311
Boundary for River Rch & Prof#=SPRING CREEK,Reach-1         , 1
Up Type= 0
Dn Type= 3
Dn Slope=0.003
Boundary for River Rch & Prof#=SPRING CREEK,Reach-1         , 2
Up Type= 0
Dn Type= 3
Dn Slope=0.003
Boundary for River Rch & Prof#=SPRING CREEK,Reach-1         , 3
Up Type= 0
Dn Type= 3
Dn Slope=0.003
Boundary for River Rch & Prof#=SPRING CREEK,Reach-1         , 4
Up Type= 0
Dn Type= 3
Dn Slope=0.003
Boundary for River Rch & Prof#=SPRING CREEK,Reach-1         , 5
Up Type= 0
Dn Type= 3
Dn Slope=0.003
Boundary for River Rch & Prof#=SPRING CREEK,Reach-1         , 6
Up Type= 0
Dn Type= 3
Dn Slope=0.003
Boundary for River Rch & Prof#=SPRING CREEK,Reach-1         , 7
Up Type= 0
Dn Type= 3
Dn Slope=0.003
DSS Import GetInterval= 0
DSS Import GetPeak= 0
DSS Import FillOption= 0

--- SPRING CREEK.g01 (geometry) ---

Geom Title=Existing Conditions
Program Version=4.10

River Reach=SPRING CREEK    ,Reach-1
Reach XY= 30
        2069175.       13850375.       2069273.8     13851465.42
      2068924.39     13851845.05      2069278.75     13853173.45
      2070017.19     13853818.81      2070080.71     13854727.58
      2070814.93     13855264.89      2071280.45     13856269.75
      2072080.45     13856872.84       2074173.5     13857078.47
      2074940.85     13857774.34      2076473.53     13857478.53
      2077130.26      13859022.9      2080531.69     13858634.29
      2081419.54     13859572.55      2081377.15     13860619.03
      2081830.93     13860922.77      2083102.35      13860574.8
      2083961.15     13861024.47      2084321.33     13860432.69
      2085831.35     13860482.43      2087821.39      13862776.5
      2087785.61     13865435.06      2089472.57     13867169.48
      2090821.81     13867132.72      2090128.22     13868717.02
      2091106.55     13868524.88      2091655.79     13868854.62
      2092718.54     13871567.27        2093525.       13870975.

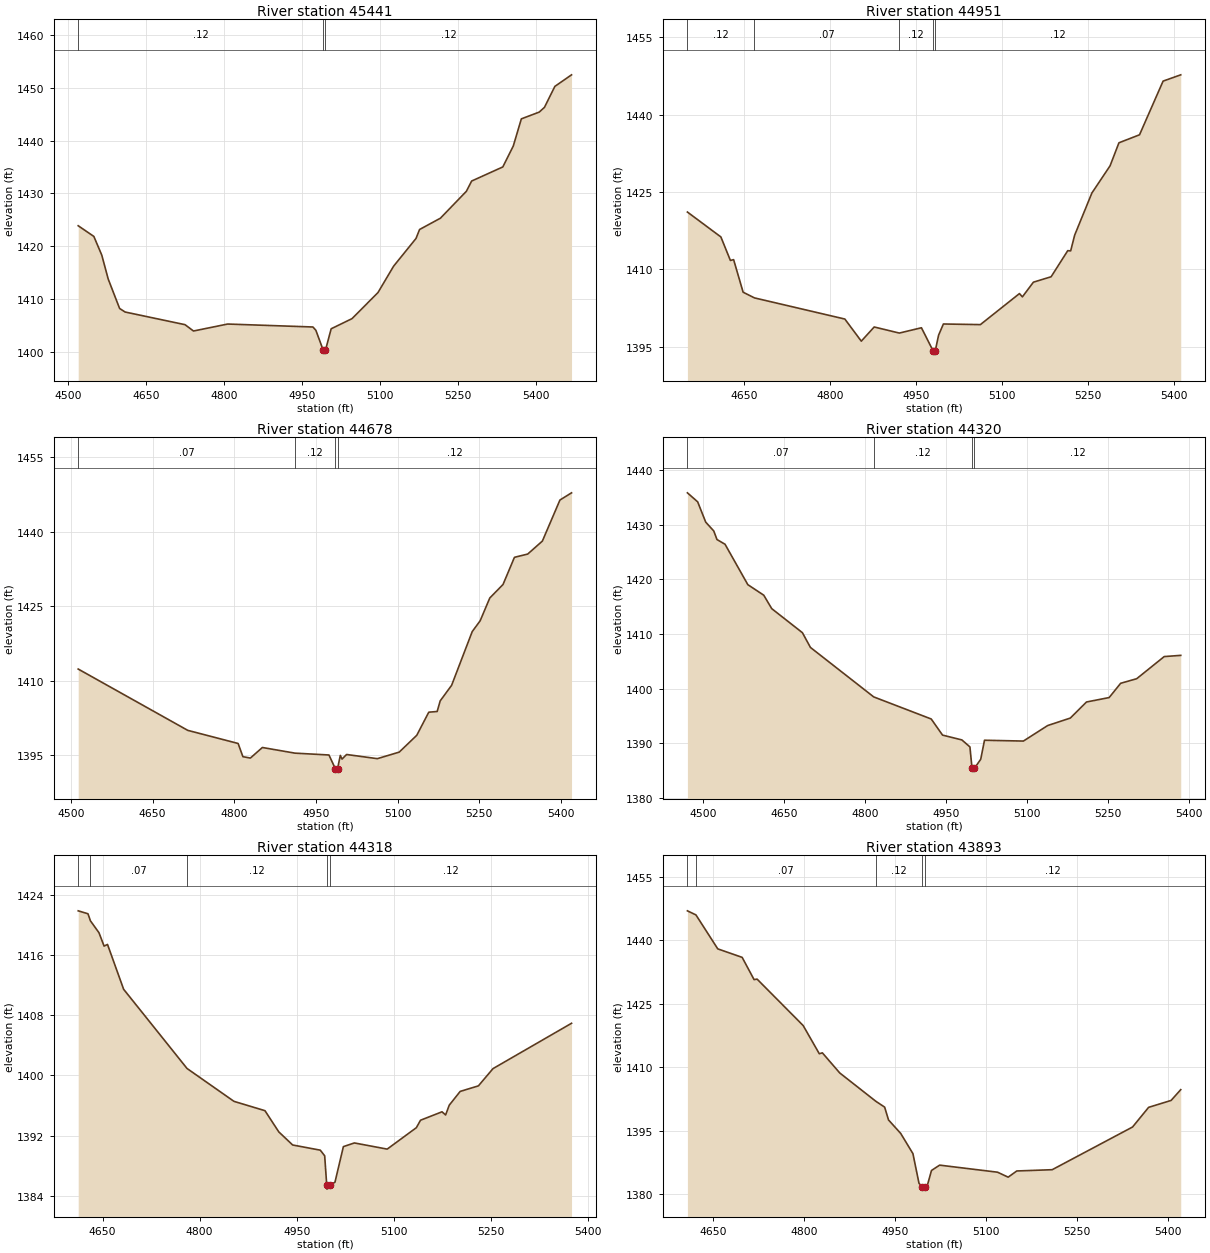
Type RM Length L Ch R = 1 ,45441   ,490,490,490
BEGIN DESCRIPTION:
SPRING CREEK_DS 83.0
END DESCRIPTION:
XS GIS Cut Line= 3
      2068824.97     13850825.02      2069248.77     13850598.15
      2069717.11     13850575.33
#Sta/Elev= 30
  4519.3 1423.88  4549.4 1421.86  4564.7 1418.31    4577  1413.8    4599 1408.21
  4609.5 1407.54  4724.9 1405.14  4741.2 1403.94    4807 1405.26  4971.1  1404.7
  4976.8 1404.07  4991.1 1400.25  4991.3 1399.75  4995.1 1400.25  5006.2 1404.36
  5046.3 1406.28  5096.3 1411.22  5126.4 1416.22  5169.5 1421.47  5176.4 1423.17
  5216.5 1425.31  5266.5 1430.41  5276.6 1432.35  5336.6 1435.02  5356.7 1438.97
  5372.3 1444.13  5406.7 1445.41  5416.7  1446.3  5436.8 1450.28  5468.9 1452.47
#Mann= 3 ,-1 , 0
  4519.3     .12       0  4991.1     .05       0  4995.1     .12       0
Bank Sta=4991.1,4995.1
XS Rating Curve= 0 ,0
Exp/Cntr=0.3,0.1

Type RM Length L Ch R = 1 ,44951   ,273,273,273
BEGIN DESCRIPTION:
SPRING CREEK_DS 82.0
END DESCRIPTION:
XS GIS Cut Line= 3
      2068874.97     13850874.98        2069275.     13851079.55
      2069674.97     13851174.99
#Sta/Elev= 30
  4550.7 1421.12  4609.1 1416.29  4625.7 1411.73  4631.3 1411.89  4647.9 1405.57
  4667.7 1404.47  4825.3 1400.37    4854 1396.08  4876.5 1398.83  4920.3 1397.65
  4958.9 1398.68    4979 1394.26  4979.3 1393.76  4983.1 1394.26  4988.8 1397.23
  4997.2 1399.41  5061.7 1399.29  5129.9 1405.31    5135 1404.67  5154.2 1407.52
  5185.1 1408.57  5214.1 1413.63  5219.2 1413.59  5226.2 1416.65  5256.2 1424.81
  5287.9 1430.08  5303.4 1434.55  5339.3  1436.1  5380.4 1446.51  5411.2 1447.73
#Mann= 5 ,-1 , 0
  4550.7     .12       0  4667.7     .07       0  4920.3     .12       0
    4979     .05       0  4983.1     .12       0
Bank Sta=4979,4983.1
XS Rating Curve= 0 ,0
Exp/Cntr=0.3,0.1

Type RM Length L Ch R = 1 ,44678   ,360,360,360
BEGIN DESCRIPTION:
SPRING CREEK_DS 81.0
END DESCRIPTION:
XS GIS Cut Line= 3
      2068875.03     13851075.02      2069275.03     13851352.28
      2069674.97     13851225.01
#Sta/Elev= 30
  4513.3 1412.33  4714.6 1399.98  4807.1 1397.34  4815.9 1394.68  4829.6  1394.4
  4851.7 1396.53  4911.6 1395.39    4974 1395.02  4985.7 1392.27    4986 1391.77
  4989.8 1392.27  4994.9 1394.94    4998 1394.19  5006.4 1395.12  5062.9 1394.28
  5103.1  1395.6  5135.3 1398.98  5157.4 1403.64  5172.8 1403.78  5178.4 1405.92
  5199.4 1409.06  5237.2 1419.87  5251.8 1422.05  5269.5 1426.64  5293.8 1429.36
  5314.8 1434.83  5339.2 1435.49  5366.1  1438.1  5398.4 1446.37  5419.7 1447.82
#Mann= 4 ,-1 , 0
  4513.3     .07       0  4911.6     .12       0  4985.7     .05       0
  4989.8     .12       0
Bank Sta=4985.7,4989.8
XS Rating Curve= 0 ,0
Exp/Cntr=0.3,0.1

Type RM Length L Ch R = 1 ,44320   ,427,427,427
BEGIN DESCRIPTION:
SPRING CREEK_DS 80.0
END DESCRIPTION:
XS GIS Cut Line= 3
      2068652.94     13851310.17      2069092.11     13851613.52
      2069407.34      13851825.8
#Sta/Elev= 30
  4470.6 1435.81  4489.6 1434.16  4504.5 1430.45  4519.4 1428.83  4525.4 1427.26
  4540.3  1426.4  4582.5 1419.01    4612 1417.08  4626.8 1414.62  4683.6 1410.22
  4698.5 1407.52  4815.7 1398.47  4922.2 1394.43  4943.2 1391.48    4979  1390.6
  4993.9 1389.32  4997.8 1385.39  4998.1 1384.89  5002.1 1385.39  5013.9 1387.06
  5020.9 1390.54  5092.9 1390.39  5137.9 1393.23  5179.9  1394.6  5209.8 1397.54
  5251.8 1398.35  5273.1 1400.96  5302.8  1401.8  5353.8 1405.85  5384.4 1406.07
#Mann= 4 ,-1 , 0
  4470.6     .07       0  4815.7     .12       0  4997.8     .05       0
  5002.1     .12       0
Bank Sta=4997.8,5002.1
XS Rating Curve= 0 ,0
Exp/Cntr=0.3,0.1

Type RM Length L Ch R = 1 ,44318   ,425,425,425
BEGIN DESCRIPTION:
SPRING CREEK_DS 80.0
END DESCRIPTION:
XS GIS Cut Line= 3
      2068724.98     13851474.99      2069092.11     13851613.52
      2069425.01     13851775.01
#Sta/Elev= 30
  4612.3 1421.89  4627.4  1421.5  4631.2 1420.56  4644.4 1418.98  4652.3  1417.2
  4657.6 1417.42  4682.5 1411.46  4780.5 1400.93    4853 1396.56  4900.9 1395.32
  4922.3  1392.5  4943.7 1390.76  4986.4 1390.07  4993.2 1389.32  4996.4 1385.39
  4996.7 1384.89  5000.7 1385.39  5009.1 1385.81  5022.1 1390.54  5039.1 1391.03
  5089.8 1390.21  5134.9 1393.06  5141.3 1394.05  5174.5 1395.17  5180.1 1394.75
  5185.7 1396.05  5202.6 1397.88  5230.8 1398.62  5253.3 1400.91  5374.7 1406.94
#Mann= 5 ,-1 , 0
  4612.3    .035       0  4631.2     .07       0  4780.5     .12       0
  4996.4     .05       0  5000.7     .12       0
Bank Sta=4996.4,5000.7
XS Rating Curve= 0 ,0
Exp/Cntr=0.3,0.1

Type RM Length L Ch R = 1 ,43893   ,492,492,492
BEGIN DESCRIPTION:
SPRING CREEK_DS 79.0
END DESCRIPTION:
XS GIS Cut Line= 3
       2068585.2     13851919.08       2068975.6     13851956.57
      2069374.99       13851825.
#Sta/Elev= 30
  4607.8 1446.99  4621.9 1446.02  4657.8    1438    4698 1435.99  4717.6 1430.74
  4722.6 1430.85  4798.5 1419.88  4825.1 1413.21  4830.1 1413.43  4858.8 1408.67
  4918.1 1401.99  4932.7  1400.6  4939.1 1397.57  4959.2 1394.38  4979.3 1389.61
  4989.3  1382.6    4995 1381.72  4995.3 1381.22  4999.4 1381.72  5002.3 1381.72
  5009.9 1385.63  5023.3 1386.89  5118.7 1385.22  5136.2 1384.05  5150.4 1385.51
  5208.7 1385.81  5341.1  1395.9  5367.6 1400.55  5404.6 1402.18  5420.5 1404.73
#Mann= 5 ,-1 , 0
  4607.8     .12       0  4621.9     .07       0  4918.1     .12       0
    4995     .05       0  4999.4     .12       0
Bank Sta=4995,4999.4
XS Rating Curve= 0 ,0
Exp/Cntr=0.3,0.1

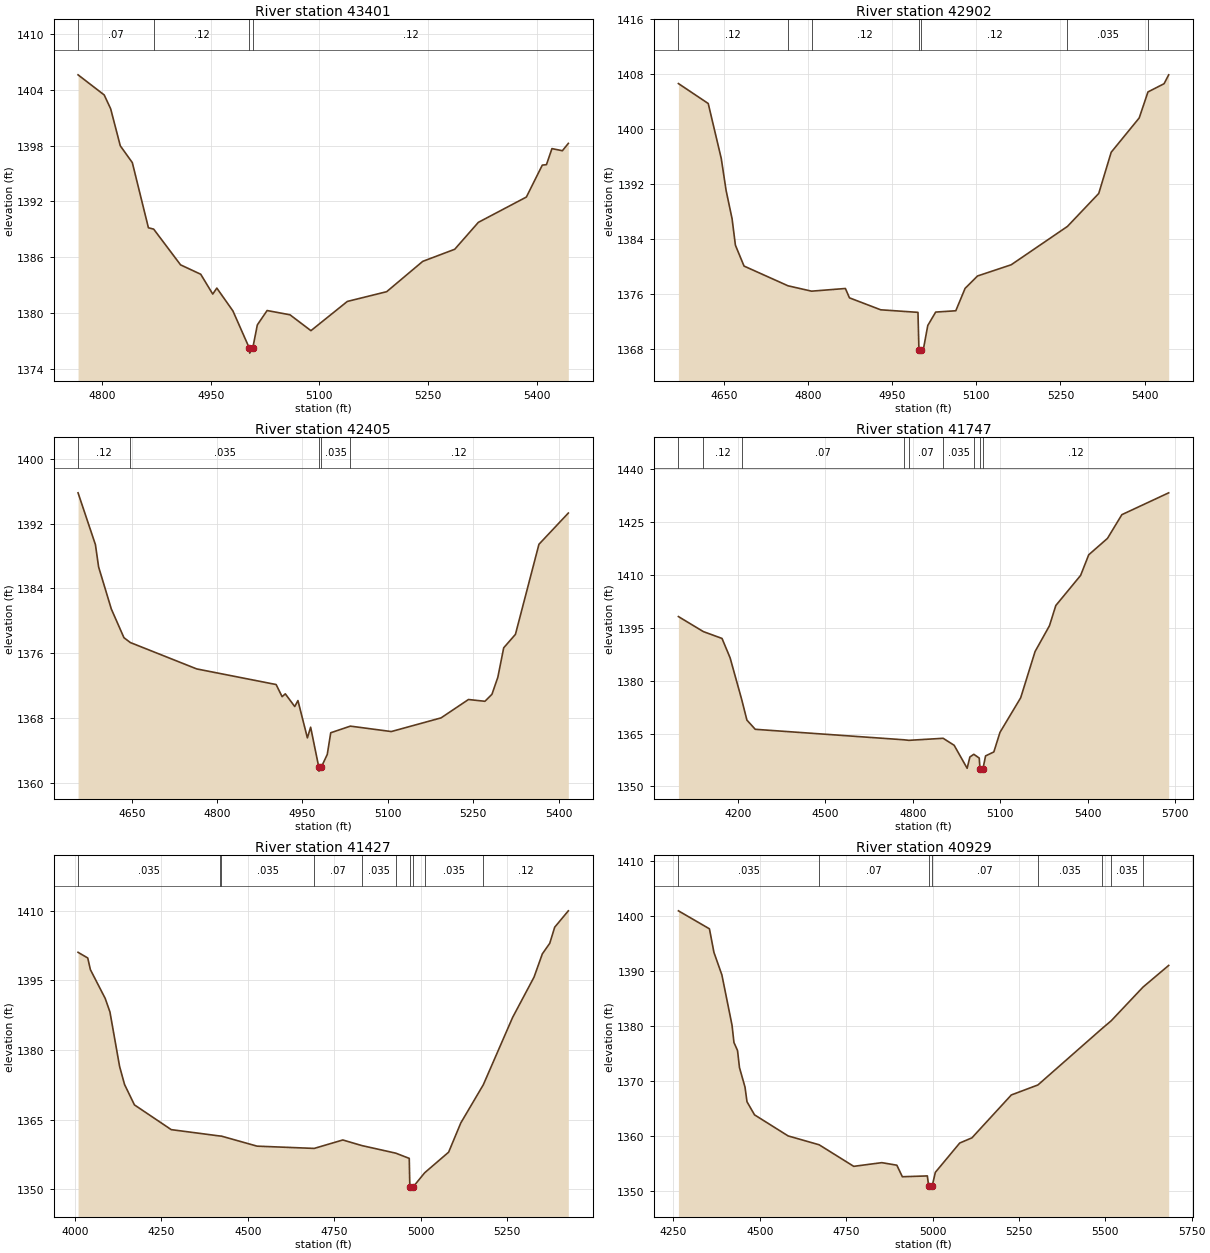
Type RM Length L Ch R = 1 ,43401   ,499,499,499
BEGIN DESCRIPTION:
SPRING CREEK_DS 78.0
END DESCRIPTION:
XS GIS Cut Line= 3
      2068874.96     13852274.98      2069082.38     13852381.33
      2069474.97     13852175.01
#Sta/Elev= 30
  4766.9 1405.65    4803 1403.48  4811.9 1401.99  4825.2    1398  4841.8 1396.19
    4864 1389.17  4871.3 1389.02  4908.4 1385.17  4936.2 1384.16  4952.8 1382.02
  4958.4 1382.67  4980.6 1380.21  5003.5 1376.16  5003.8 1375.66  5007.9 1376.16
  5014.3  1378.7  5027.8 1380.25  5059.4 1379.79  5088.3 1378.08  5138.5 1381.23
  5192.8 1382.28  5242.6 1385.55  5286.7 1386.85  5319.3 1389.75  5385.6 1392.48
  5407.6 1395.92  5413.3 1395.97  5420.9  1397.7  5435.3 1397.47  5443.5 1398.26
#Mann= 4 ,-1 , 0
  4766.9     .07       0  4871.3     .12       0  5003.5     .05       0
  5007.9     .12       0
Bank Sta=5003.5,5007.9
XS Rating Curve= 0 ,0
Exp/Cntr=0.3,0.1

Type RM Length L Ch R = 1 ,42902   ,497,497,497
BEGIN DESCRIPTION:
SPRING CREEK_DS 77.0
END DESCRIPTION:
XS GIS Cut Line= 3
      2068874.99     13852925.01      2069280.75     13852777.34
      2069674.97     13852575.02
#Sta/Elev= 30
  4568.2 1406.64  4621.4 1403.74  4644.7 1395.73  4653.3 1391.09    4664 1386.97
  4669.9 1383.14  4685.3  1380.1  4763.8 1377.23  4805.8 1376.45  4866.2 1376.84
  4873.4 1375.48  4929.2 1373.74  4995.7 1373.37  4997.4 1367.94  4997.7 1367.44
  5001.9 1367.94  5005.2 1367.94  5013.2 1371.46  5027.3 1373.41  5063.2  1373.6
  5079.8 1376.86    5102 1378.66  5162.1 1380.29  5262.5 1385.87  5318.3 1390.66
  5340.5 1396.65  5390.5 1401.64  5406.1 1405.42  5434.9 1406.62  5443.1 1407.91
#Mann= 7 ,-1 , 0
  4568.2     .12       0  4763.8     .07       0  4805.8     .12       0
  4997.4     .05       0  5001.9     .12       0  5262.5    .035       0
  5406.1     .12       0
Bank Sta=4997.4,5001.9
XS Rating Curve= 0 ,0
Exp/Cntr=0.3,0.1

Type RM Length L Ch R = 1 ,42405   ,978,978,978
BEGIN DESCRIPTION:
SPRING CREEK_DS 76.0
END DESCRIPTION:
XS GIS Cut Line= 3
      2068925.03     13853025.02      2069320.77     13853226.78
      2069725.05     13853124.99
#Sta/Elev= 30
  4555.8 1395.82  4586.3 1389.42  4591.9 1386.66  4614.2 1381.47  4636.4 1377.92
  4647.6 1377.32  4764.2 1374.06  4903.7 1372.13  4914.2 1370.63  4919.8 1370.98
  4936.4 1369.41    4942 1370.15  4958.6 1365.54  4964.3 1366.86  4978.6 1361.93
  4978.9 1361.43  4983.1 1361.93  4993.5 1363.49  4999.6 1366.17  5034.1 1366.99
    5106 1366.32  5193.4 1368.01  5241.5 1370.28  5270.4 1370.06  5282.8 1370.93
  5293.1 1373.03  5303.4 1376.67    5324 1378.33  5365.3 1389.46  5416.9 1393.32
#Mann= 5 ,-1 , 0
  4555.8     .12       0  4647.6    .035       0  4978.6    .035       0
  4983.1    .035       0  5034.1     .12       0
Bank Sta=4978.6,4983.1
XS Rating Curve= 0 ,0
Exp/Cntr=0.3,0.1

Type RM Length L Ch R = 1 ,41747   ,320,320,320
BEGIN DESCRIPTION:
SPRING CREEK_DS 75.5
END DESCRIPTION:
XS GIS Cut Line= 3
      2069220.18     13854417.57      2069793.74     13853596.68
      2070246.48     13853089.73
#Sta/Elev= 30
  3996.5  1398.2  4081.8 1393.94    4146 1391.99  4173.7  1386.5  4213.4 1374.69
  4231.4 1368.81    4260  1366.2  4768.9 1363.23  4786.8 1363.07  4904.3 1363.65
    4942 1361.66  4986.5 1355.14  4995.9 1358.34  5009.4 1359.11    5028 1358.04
  5030.7 1354.83  5031.2 1354.33  5040.3 1354.83  5049.7 1358.65  5078.1 1359.78
  5099.1 1365.33  5170.1 1375.15  5219.4 1388.27  5268.8  1395.6  5290.5 1401.33
  5375.6 1409.88  5403.4 1415.73  5467.7 1420.39    5517 1427.12  5677.6 1433.32
#Mann= 9 ,-1 , 0
  3996.5    .035       0  4081.8     .12       0  4213.4     .07       0
  4768.9    .035       0  4786.8     .07       0  4904.3    .035       0
  5009.4     .12       0  5030.7    .035       0  5040.3     .12       0
Bank Sta=5030.7,5040.3
XS Rating Curve= 0 ,0
Exp/Cntr=0.3,0.1

Type RM Length L Ch R = 1 ,41427   ,498,498,498
BEGIN DESCRIPTION:
SPRING CREEK_DS 75.0
END DESCRIPTION:
XS GIS Cut Line= 3
      2069374.98     13854575.03      2070019.54     13853822.55
      2070175.01     13853424.97
#Sta/Elev= 30
  4009.2 1401.07  4037.2 1399.85  4044.9 1397.33  4087.7 1391.13  4101.4 1388.21
  4129.4 1376.43  4143.7 1372.56  4172.2 1368.17  4278.7 1362.83    4421 1361.44
  4422.9 1361.45  4526.8 1359.27    4692 1358.78  4774.8  1360.6    4830 1359.39
  4927.8 1357.76  4966.9 1356.63  4968.6  1350.5  4969.1    1350  4978.4  1350.5
  5011.5 1353.53  5080.8 1357.97    5116 1364.28    5181  1372.5  5265.8 1387.03
  5327.8 1395.73  5351.7 1400.73  5373.2 1403.02  5387.5 1406.49  5426.9 1410.02
#Mann= 10 ,-1 , 0
  4009.2    .035       0    4421     .07       0  4422.9    .035       0
    4692     .07       0    4830    .035       0  4927.8     .07       0
  4968.6     .05       0  4978.4     .07       0  5011.5    .035       0
    5181     .12       0
Bank Sta=4968.6,4978.4
XS Rating Curve= 0 ,0
Exp/Cntr=0.3,0.1

Type RM Length L Ch R = 1 ,40929   ,499,499,499
BEGIN DESCRIPTION:
SPRING CREEK_DS 74.0
END DESCRIPTION:
XS GIS Cut Line= 3
      2069415.03      13854665.6      2070058.15     13854308.52
      2070597.67      13853888.9
#Sta/Elev= 30
  4264.4 1400.89  4354.2 1397.62  4367.3 1393.32  4390.2 1389.25  4419.5 1380.14
  4425.2 1376.96  4435.5 1375.51  4441.2 1372.39  4457.2 1368.85  4462.9  1366.2
  4484.7 1363.82  4581.9 1359.99  4671.7 1358.38  4771.9 1354.46  4853.1 1355.13
  4896.6 1354.67  4912.6 1352.57    4985 1352.72  4988.9 1350.82  4989.4 1350.32
  4998.7 1350.82  5008.1 1353.37  5078.7  1358.7    5114 1359.64    5228 1367.43
    5305 1369.25  5489.9 1379.46  5517.1 1380.91    5609 1387.02  5683.5 1390.97
#Mann= 8 ,-1 , 0
  4264.4    .035       0  4671.7     .07       0  4988.9     .05       0
  4998.7     .07       0    5305    .035       0  5489.9     .07       0
  5517.1    .035       0    5609     .07       0
Bank Sta=4988.9,4998.7
XS Rating Curve= 0 ,0
Exp/Cntr=0.3,0.1

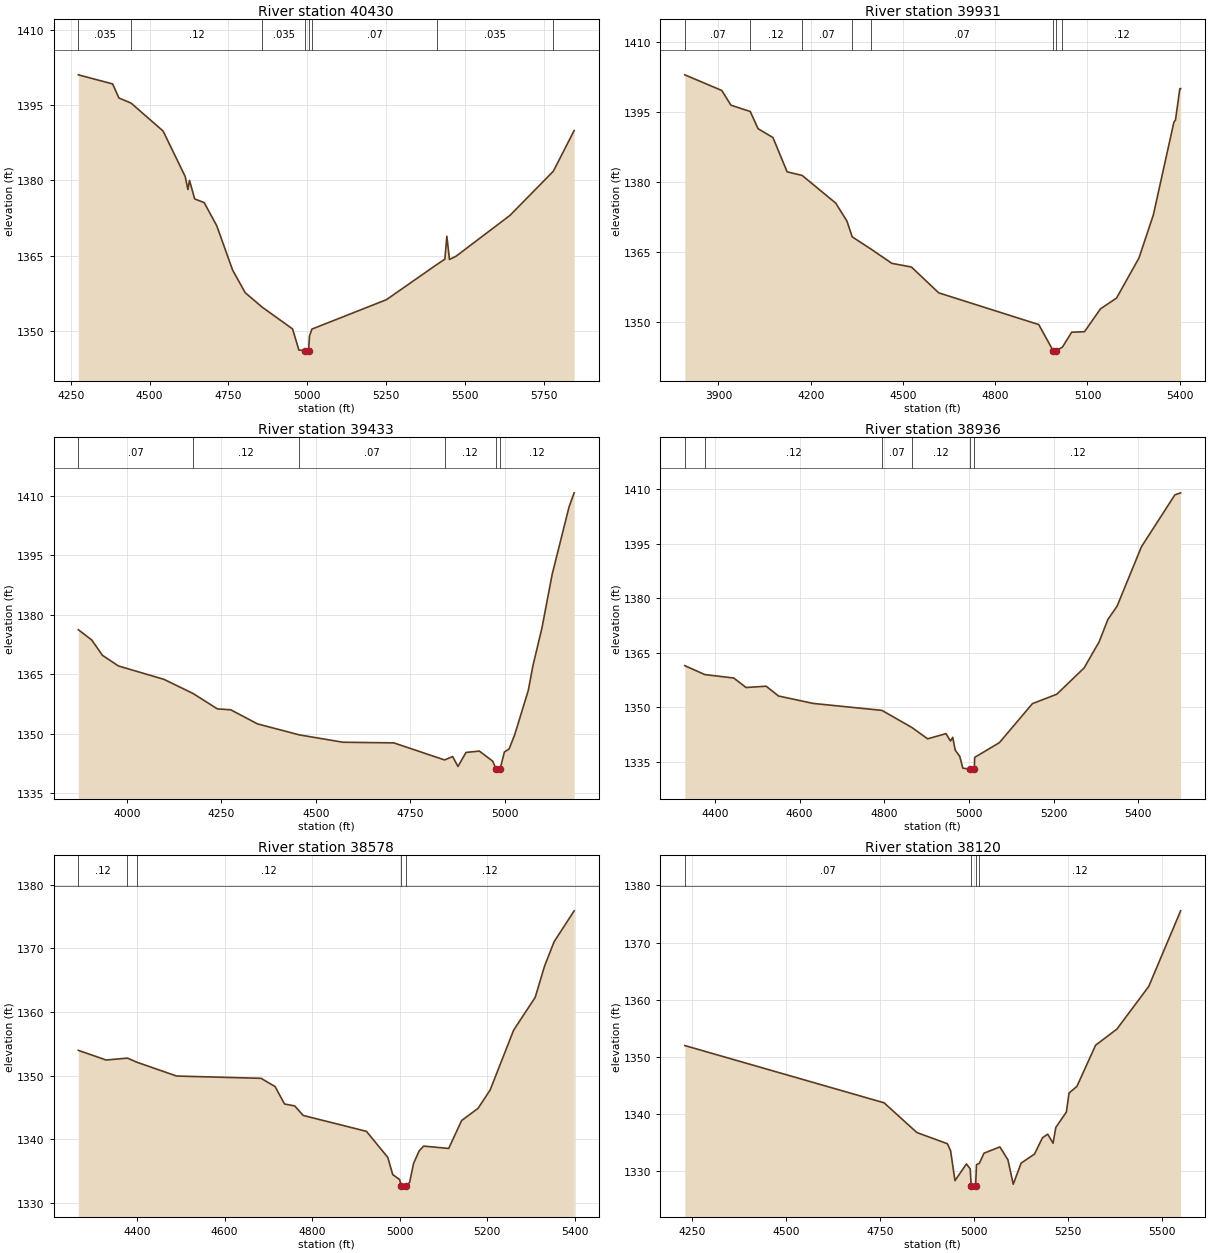
Type RM Length L Ch R = 1 ,40430   ,499,499,499
BEGIN DESCRIPTION:
SPRING CREEK_DS 73.0
END DESCRIPTION:
XS GIS Cut Line= 3
      2069366.37     13854776.72      2070091.45     13854742.14
      2070769.15     13854235.08
#Sta/Elev= 30
  4274.1    1401  4382.9 1399.19  4402.9 1396.39  4441.1 1395.39    4543 1389.81
  4613.1 1380.75  4621.6 1378.17  4626.6 1380.01  4643.1 1376.31  4673.2 1375.58
  4713.2 1370.95  4763.3 1362.16  4803.3 1357.65  4857.3 1354.77  4953.5 1350.44
  4973.5 1346.24  4994.3 1346.13  4994.8 1345.63  5004.3 1346.13  5007.1 1349.03
  5014.8 1350.41    5251 1356.26    5411 1363.26  5436.4 1364.33  5442.7 1368.89
    5451 1364.26  5471.9 1364.91  5642.8 1373.03  5780.5 1381.83  5846.4 1389.92
#Mann= 8 ,-1 , 0
  4274.1    .035       0  4441.1     .12       0  4857.3    .035       0
  4994.3    .035       0  5004.3    .035       0  5014.8     .07       0
    5411    .035       0  5780.5     .07       0
Bank Sta=4994.3,5004.3
XS Rating Curve= 0 ,0
Exp/Cntr=0.3,0.1

Type RM Length L Ch R = 1 ,39931   ,498,498,498
BEGIN DESCRIPTION:
SPRING CREEK_DS 72.0
END DESCRIPTION:
XS GIS Cut Line= 3
      2069362.93      13855679.5      2070388.37     13855038.32
      2070775.01       13854925.
#Sta/Elev= 30
  3790.6 1402.96    3911 1399.61  3940.5 1396.47  4003.5 1395.11  4028.9 1391.43
  4077.3 1389.54  4123.3 1382.21  4172.3 1381.43  4281.3 1375.52  4317.8 1371.67
    4335 1368.29  4396.3 1365.66    4464 1362.62  4527.7 1361.83  4616.2 1356.31
  4941.6 1349.52  4988.5 1343.91    4989 1343.41  4998.5 1343.91  5018.7 1344.71
  5048.6 1347.89  5090.3 1347.99  5142.4 1352.89  5194.5 1355.19  5267.4 1363.76
  5314.2 1372.98    5381 1392.82  5386.2 1393.28  5400.3    1400  5402.9    1400
#Mann= 8 ,-1 , 0
  3790.6     .07       0  4003.5     .12       0  4172.3     .07       0
    4335     .12       0  4396.3     .07       0  4988.5     .05       0
  4998.5     .07       0  5018.7     .12       0
Bank Sta=4988.5,4998.5
XS Rating Curve= 0 ,0
Exp/Cntr=0.3,0.1

Type RM Length L Ch R = 1 ,39433   ,497,497,497
BEGIN DESCRIPTION:
SPRING CREEK_DS 71.0
END DESCRIPTION:
XS GIS Cut Line= 3
      2069974.97     13856025.03      2070773.64     13855228.04
        2070925.       13855125.
#Sta/Elev= 30
  3871.7 1376.26  3907.1 1373.68  3935.4 1369.81  3977.8 1367.12    4098 1363.76
  4175.3 1360.18  4239.4 1356.31  4274.8 1356.08  4345.5 1352.53  4456.4 1349.75
  4571.8  1347.9  4706.1 1347.74  4840.4 1343.44  4861.7  1344.3  4875.8 1341.79
    4897 1345.33  4932.4 1345.67  4967.8 1343.12  4976.7 1341.12  4977.2 1340.62
  4987.1 1341.12  4998.6 1345.45    5011  1346.2  5025.8 1349.78  5061.8 1360.97
  5074.2 1367.25  5097.8 1376.64  5124.8 1390.16  5169.6  1407.2  5183.1 1410.76
#Mann= 6 ,-1 , 0
  3871.7     .07       0  4175.3     .12       0  4456.4     .07       0
  4840.4     .12       0  4976.7     .05       0  4987.1     .12       0
Bank Sta=4976.7,4987.1
XS Rating Curve= 0 ,0
Exp/Cntr=0.3,0.1

Type RM Length L Ch R = 1 ,38936   ,358,358,358
BEGIN DESCRIPTION:
SPRING CREEK_DS 70.0
END DESCRIPTION:
XS GIS Cut Line= 3
      2070206.71     13855936.43      2070824.92     13855675.03
      2071125.02     13855274.98
#Sta/Elev= 30
  4328.8 1361.41  4376.1 1358.96  4444.5 1358.01  4473.6  1355.4    4521 1355.76
  4550.1 1353.07  4632.1 1351.02  4794.5 1349.11  4865.8 1344.36  4902.4 1341.28
  4945.8 1342.71  4956.4 1340.68  4961.8  1341.7  4967.5  1338.2  4978.4 1336.43
  4985.5 1333.23  5002.1 1332.89  5002.6 1332.39  5012.6 1332.89  5013.6 1336.17
    5072 1340.23  5150.1 1350.97  5207.4 1353.54    5272 1360.77  5307.4 1367.92
  5328.2  1374.1  5350.1 1377.81  5407.4  1394.1  5486.5 1408.41  5500.1 1408.97
#Mann= 6 ,-1 , 0
  4328.8     .07       0  4376.1     .12       0  4794.5     .07       0
  4865.8     .12       0  5002.1     .05       0  5012.6     .12       0
Bank Sta=5002.1,5012.6
XS Rating Curve= 0 ,0
Exp/Cntr=0.3,0.1

Type RM Length L Ch R = 1 ,38578   ,458,458,458
BEGIN DESCRIPTION:
SPRING CREEK_DS 69.0
END DESCRIPTION:
XS GIS Cut Line= 3
      2070345.62     13856186.42      2071030.64     13855922.52
      2071225.01     13855574.98
#Sta/Elev= 30
  4265.9 1353.96  4329.5 1352.44    4378 1352.74  4399.8 1352.09  4490.3 1349.92
  4683.2 1349.56  4715.3 1348.26  4736.8 1345.52  4760.1 1345.22  4779.4 1343.72
  4923.9 1341.22  4972.5 1337.13  4983.9 1334.42  4999.7 1333.63  5003.3 1332.63
  5003.8 1332.13  5013.9 1332.63  5022.5  1333.2  5031.5 1336.18  5044.2 1338.14
  5054.4  1338.9  5111.7 1338.53  5141.2 1342.92  5178.9 1344.85  5206.3 1347.72
    5260 1357.14  5309.1 1362.28  5330.8 1367.26  5352.5 1371.06  5398.2 1375.91
#Mann= 5 ,-1 , 0
  4265.9     .12       0    4378     .07       0  4399.8     .12       0
  5003.3     .05       0  5013.9     .12       0
Bank Sta=5003.3,5013.9
XS Rating Curve= 0 ,0
Exp/Cntr=0.3,0.1

Type RM Length L Ch R = 1 ,38120   ,535,535,535
BEGIN DESCRIPTION:
SPRING CREEK_DS 68.0
END DESCRIPTION:
XS GIS Cut Line= 3
      2070515.68     13856377.42      2071283.08     13856248.94
      2071675.02     13855874.98
#Sta/Elev= 30
  4230.3 1351.99  4760.8 1341.98  4848.1 1336.78  4929.2 1334.83  4937.8 1333.61
  4949.5 1328.38  4979.9 1331.29  4990.1 1330.41  4992.7 1327.39  4993.2 1326.89
  5004.3 1327.39  5006.8 1331.18  5014.3 1331.39  5026.6 1333.17    5069 1334.27
  5090.4 1332.02  5104.6 1327.75  5125.6 1331.44  5161.2 1333.02  5182.2 1335.86
  5196.4  1336.5  5210.6 1334.92  5217.8 1337.67    5246 1340.37    5253 1343.67
  5274.1 1344.86  5323.8 1352.05  5380.4 1354.86  5465.3 1362.33  5550.1 1375.54
#Mann= 4 ,-1 , 0
  4230.3     .07       0  4992.7     .05       0  5004.3     .07       0
  5014.3     .12       0
Bank Sta=4992.7,5004.3
XS Rating Curve= 0 ,0
Exp/Cntr=0.3,0.1

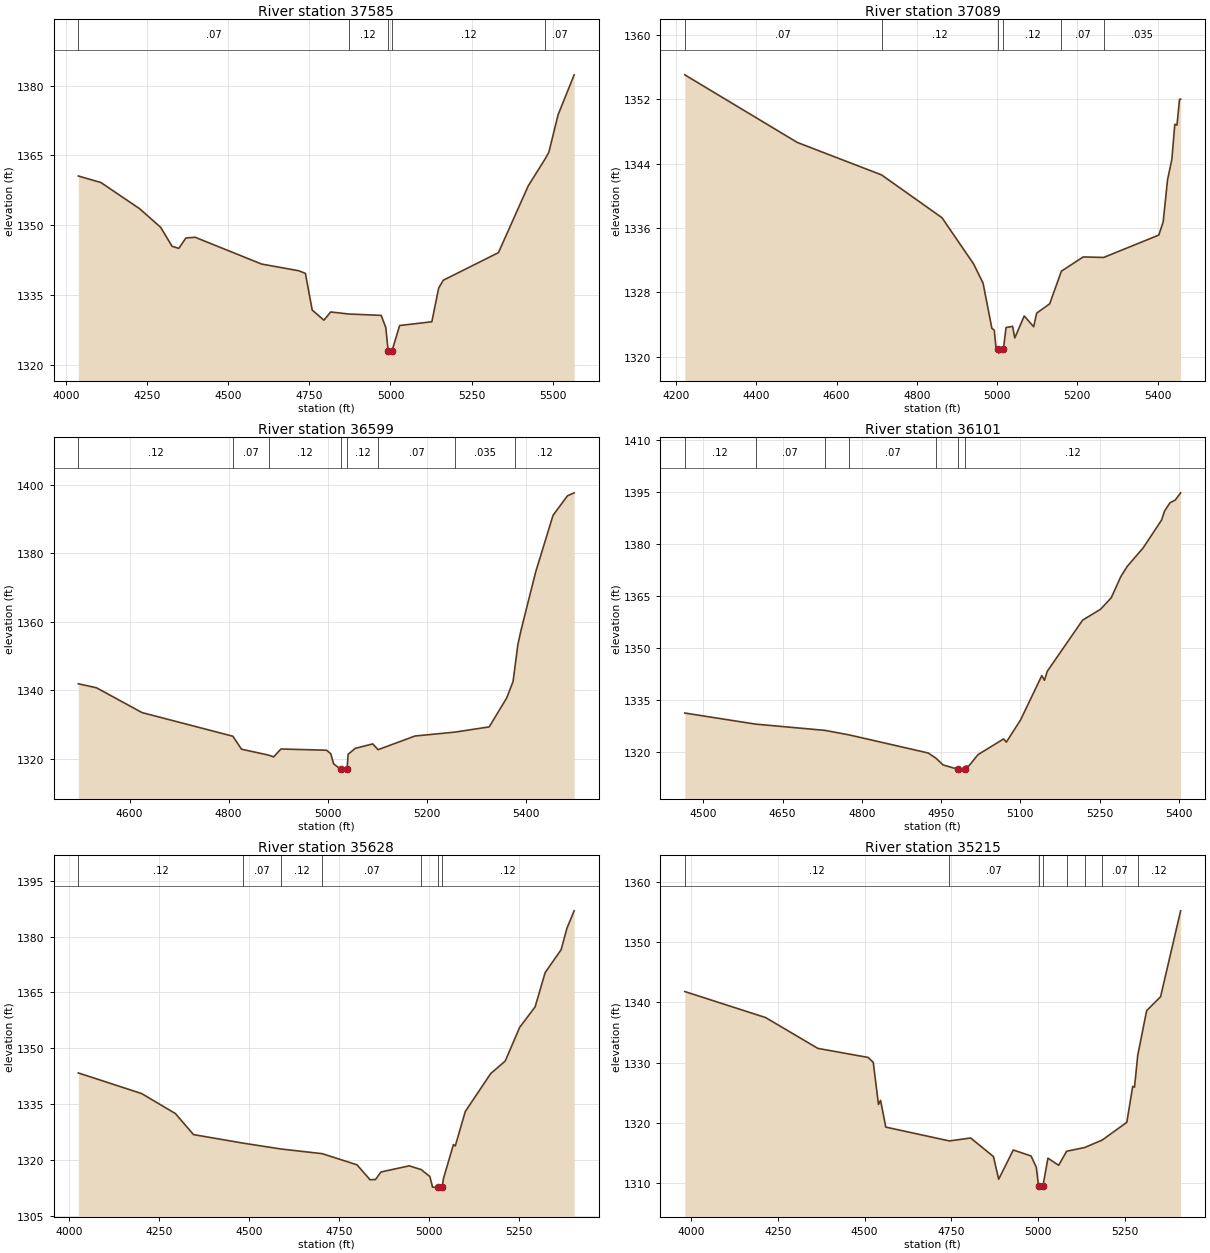
Type RM Length L Ch R = 1 ,37585   ,496,496,496
BEGIN DESCRIPTION:
SPRING CREEK_DS 67.0
END DESCRIPTION:
XS GIS Cut Line= 3
       2070932.4      13857189.9      2071658.33     13856558.35
      2072075.01     13856174.99
#Sta/Elev= 30
  4037.8 1360.58  4107.4 1359.18    4227 1353.53  4291.6 1349.54  4326.7 1345.47
  4347.5 1345.01  4369.4 1347.25  4397.9  1347.4    4603 1341.63  4716.9  1340.2
  4737.8 1339.63  4758.7 1331.74  4794.8 1329.56  4815.7 1331.33  4870.8 1330.89
  4971.4 1330.59  4985.6 1327.97  4992.9 1322.97  4993.4 1322.47  5004.6 1322.97
  5028.3 1328.41  5127.5 1329.22  5148.5 1336.45  5162.7 1338.15  5332.8 1344.09
  5424.7 1358.46  5476.9 1364.28  5488.2 1365.69  5516.6 1373.74  5566.2 1382.35
#Mann= 5 ,-1 , 0
  4037.8     .07       0  4870.8     .12       0  4992.9     .05       0
  5004.6     .12       0  5476.9     .07       0
Bank Sta=4992.9,5004.6
XS Rating Curve= 0 ,0
Exp/Cntr=0.3,0.1

Type RM Length L Ch R = 1 ,37089   ,490,490,490
BEGIN DESCRIPTION:
SPRING CREEK_DS 66.0
END DESCRIPTION:
XS GIS Cut Line= 3
      2071626.84      13857502.4       2072044.8     13856845.49
      2072225.01     13856424.98
#Sta/Elev= 30
  4221.4 1355.04  4501.8 1346.64  4712.1  1342.6  4862.5 1337.29  4941.3 1331.55
    4965 1329.16  4986.9 1323.55  4992.9 1323.31  4997.3 1321.11  5003.4 1320.96
  5003.9 1320.46  5015.7 1320.96  5022.3 1323.64  5038.6 1323.79  5044.1 1322.35
  5067.6 1325.08  5091.2 1323.74  5098.5 1325.42  5131.1 1326.59  5160.2 1330.64
  5214.5 1332.41  5265.8 1332.35  5403.1 1335.13    5414 1336.76  5424.8 1341.97
  5435.7 1344.56    5443  1348.9  5448.4 1348.79  5454.8 1352.01  5457.5 1352.01
#Mann= 6 ,-1 , 0
  4221.4     .07       0  4712.1     .12       0  5003.4     .05       0
  5015.7     .12       0  5160.2     .07       0  5265.8    .035       0
Bank Sta=5003.4,5015.7
XS Rating Curve= 0 ,0
Exp/Cntr=0.3,0.1

Type RM Length L Ch R = 1 ,36599   ,498,498,498
BEGIN DESCRIPTION:
SPRING CREEK_DS 65.0
END DESCRIPTION:
XS GIS Cut Line= 3
      2072175.02     13857224.97      2072472.67     13856819.24
      2072774.99     13856425.02
#Sta/Elev= 30
  4496.8 1341.95  4533.4 1340.78  4625.3 1333.54  4808.5 1326.64  4825.9 1322.86
  4880.9 1321.12  4890.7 1320.61  4905.4 1322.92  4997.3 1322.56  5005.8 1321.57
  5011.8 1318.56  5026.5 1316.96    5027 1316.46  5038.8 1316.96  5040.9 1321.37
  5055.4 1323.11  5090.7  1324.4  5101.3 1322.72  5175.9 1326.71  5256.2 1327.84
  5325.5 1329.37  5360.8 1337.83  5373.6 1342.63  5377.3 1346.74  5383.4 1353.51
  5389.9 1357.69  5418.9 1374.41  5454.2 1391.09  5483.3 1396.79  5496.8 1397.66
#Mann= 8 ,-1 , 0
  4496.8     .12       0  4808.5     .07       0  4880.9     .12       0
  5026.5     .05       0  5038.8     .12       0  5101.3     .07       0
  5256.2    .035       0  5377.3     .12       0
Bank Sta=5026.5,5038.8
XS Rating Curve= 0 ,0
Exp/Cntr=0.3,0.1

Type RM Length L Ch R = 1 ,36101   ,473,473,473
BEGIN DESCRIPTION:
SPRING CREEK_DS 64.0
END DESCRIPTION:
XS GIS Cut Line= 3
      2072574.97     13857275.04      2072929.72     13856874.57
        2072875.       13856475.
#Sta/Elev= 30
    4465 1331.28  4598.8 1328.08  4730.5 1326.27  4776.3 1324.96  4925.5 1319.75
  4940.4 1318.23  4953.9 1316.29  4982.8 1315.01  4983.3 1314.51  4995.3 1315.01
  4996.4 1315.96  5002.3 1315.96  5019.8 1319.26  5068.4 1323.81  5073.5 1322.88
  5100.5 1329.31  5140.6 1342.08  5145.6 1340.74    5151 1343.34  5217.8 1358.09
  5251.9 1361.25  5272.1 1364.57    5290 1370.63  5302.4 1373.63  5332.6 1378.99
  5367.2 1386.97    5373  1389.6  5383.1 1391.96  5393.2 1392.77  5403.3 1394.84
#Mann= 7 ,-1 , 0
    4465     .12       0  4598.8     .07       0  4730.5     .12       0
  4776.3     .07       0  4940.4     .12       0  4982.8     .05       0
  4995.3     .12       0
Bank Sta=4982.8,4995.3
XS Rating Curve= 0 ,0
Exp/Cntr=0.3,0.1

Type RM Length L Ch R = 1 ,35628   ,413,413,413
BEGIN DESCRIPTION:
SPRING CREEK_DS 63.0
END DESCRIPTION:
XS GIS Cut Line= 3
      2072842.09     13857794.11      2073370.48     13856974.94
      2073424.99     13856575.04
#Sta/Elev= 30
  4025.2 1343.36  4201.3 1337.81    4295 1332.44  4345.4 1326.78  4481.7 1324.51
  4588.5 1322.91  4703.3 1321.65  4799.9 1318.66  4836.2 1314.64  4851.4 1314.71
  4866.5 1316.73  4945.1 1318.38  4978.2 1317.38  5002.5  1315.5    5010 1312.64
  5023.9 1312.62  5024.4 1312.12  5036.5 1312.62  5040.3 1314.97    5068  1324.1
  5073.1 1323.72  5100.9 1332.98  5171.5 1343.18  5211.9 1346.55  5252.2 1355.62
  5295.1 1361.13  5322.9 1370.32  5367.5 1376.51  5383.5 1382.26  5403.6 1386.94
#Mann= 7 ,-1 , 0
  4025.2     .12       0  4481.7     .07       0  4588.5     .12       0
  4703.3     .07       0  4978.2     .12       0  5023.9     .05       0
  5036.5     .12       0
Bank Sta=5023.9,5036.5
XS Rating Curve= 0 ,0
Exp/Cntr=0.3,0.1

Type RM Length L Ch R = 1 ,35215   ,497,497,497
BEGIN DESCRIPTION:
SPRING CREEK_DS 62.0
END DESCRIPTION:
XS GIS Cut Line= 3
      2073171.96     13857974.65      2073730.45     13857122.81
      2073624.99     13856724.95
#Sta/Elev= 30
  3981.4 1341.81  4214.5 1337.48  4365.2 1332.35  4509.9 1330.85    4525 1330.03
  4540.1 1323.02  4546.1  1323.7  4561.2 1319.25  4744.6 1316.95  4806.1 1317.44
  4871.7 1314.35  4886.8 1310.58  4928.9 1315.44  4980.2 1314.45  4995.3 1312.57
  5001.8 1309.43  5002.3 1308.93  5014.4 1309.43  5028.8 1314.08  5059.8  1312.9
  5082.7 1315.23  5135.1 1315.86  5185.3 1317.09  5256.4 1320.05  5273.4 1326.03
  5278.6  1325.9  5287.9  1331.2  5313.6 1338.63  5353.8 1340.95  5411.6 1355.24
#Mann= 8 ,-1 , 0
  3981.4     .12       0  4744.6     .07       0  5001.8     .05       0
  5014.4     .07       0  5082.7     .07       0  5135.1     .12       0
  5185.3     .07       0  5287.9     .12       0
Bank Sta=5001.8,5014.4
XS Rating Curve= 0 ,0
Exp/Cntr=0.3,0.1

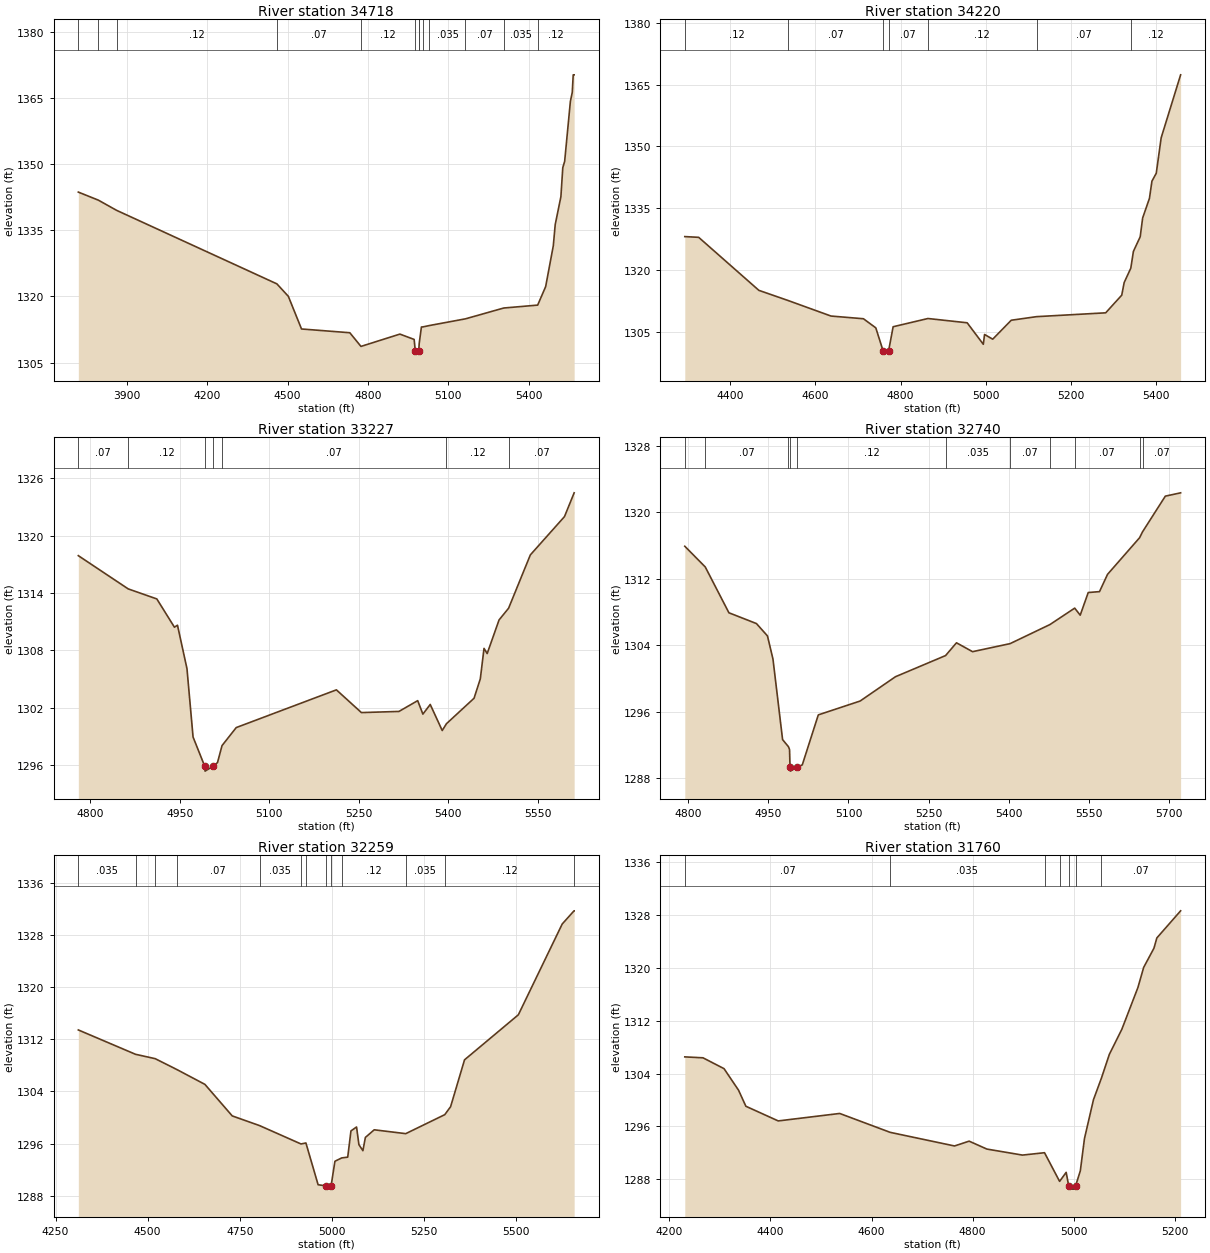
Type RM Length L Ch R = 1 ,34718   ,498,498,498
BEGIN DESCRIPTION:
SPRING CREEK_DS 61.0
END DESCRIPTION:
XS GIS Cut Line= 3
      2073779.62     13858297.52       2074173.5     13857078.47
        2074575.       13856675.
#Sta/Elev= 30
  3718.9 1343.65  3793.6 1341.83  3861.7 1339.52  4459.9 1322.86  4502.6 1320.04
  4551.8 1312.64    4732 1311.79  4773.6 1308.69  4918.9 1311.48  4972.1 1310.27
  4976.3 1307.67  4976.8 1307.17    4989 1307.67  4991.1 1309.42  4999.2 1313.09
  5005.6 1313.12  5029.1 1313.42  5163.7 1314.94  5306.4 1317.39  5433.1 1318.05
  5462.9 1322.25  5491.4  1331.5  5498.5 1336.29  5519.7 1342.61  5526.8 1349.19
  5533.8 1350.64  5555.1 1364.19  5562.1 1366.24  5565.7 1370.22  5569.2 1370.22
#Mann= 13 ,-1 , 0
  3718.9     .07       0  3793.6    .035       0  3861.7     .12       0
  4459.9     .07       0  4773.6     .12       0  4976.3     .05       0
    4989     .12       0  4991.1     .07       0  5005.6     .12       0
  5029.1    .035       0  5163.7     .07       0  5306.4    .035       0
  5433.1     .12       0
Bank Sta=4976.3,4989
XS Rating Curve= 0 ,0
Exp/Cntr=0.3,0.1

Type RM Length L Ch R = 1 ,34220   ,993,993,993
BEGIN DESCRIPTION:
SPRING CREEK_DS 60.0
END DESCRIPTION:
XS GIS Cut Line= 3
      2074324.99     13857925.02      2074602.28     13857274.99
      2074824.99     13856875.02
#Sta/Elev= 30
  4293.3 1328.11  4325.9 1327.93  4467.3 1315.05    4536 1312.58  4636.6 1308.81
  4712.9 1308.15  4741.9 1305.94  4759.2  1300.3  4759.7  1299.8  4771.9  1300.3
  4782.6 1306.21  4864.4 1308.21  4956.5 1307.17  4994.4 1301.95  4997.3 1304.33
  5016.5 1303.19    5060 1307.79  5119.4 1308.66  5281.8 1309.59  5319.5 1313.88
  5325.2 1316.94  5340.8 1320.44  5346.9 1324.51  5362.9 1328.08  5368.6 1332.63
  5384.6 1337.41  5390.4 1341.57  5400.6  1343.5  5412.1 1352.11  5457.8 1367.41
#Mann= 7 ,-1 , 0
  4293.3     .12       0    4536     .07       0  4759.2     .05       0
  4771.9     .07       0  4864.4     .12       0  5119.4     .07       0
  5340.8     .12       0
Bank Sta=4759.2,4771.9
XS Rating Curve= 0 ,0
Exp/Cntr=0.3,0.1

Type RM Length L Ch R = 1 ,33227   ,487,487,487
BEGIN DESCRIPTION:
SPRING CREEK_DS 59.0
END DESCRIPTION:
XS GIS Cut Line= 3
      2075125.01     13857974.95      2075158.25     13857757.68
      2074975.01     13857175.02
#Sta/Elev= 30
  4780.2 1317.91  4863.8 1314.43  4911.7 1313.38  4941.2 1310.42  4946.3 1310.63
  4962.2 1306.08  4972.4 1298.92    4992 1295.85  4992.5 1295.35  5005.6 1295.85
  5013.3 1296.24  5020.9 1298.02  5044.7 1299.91  5212.5 1303.86  5254.4 1301.48
  5317.3  1301.6  5348.7 1302.73  5357.4 1301.32  5369.7 1302.33  5389.8  1299.6
  5396.8 1300.31  5443.1 1302.98  5453.6 1305.01  5459.8  1308.2  5465.1 1307.66
    5485 1311.18    5501 1312.41  5537.4 1317.99  5594.6    1322  5610.8 1324.49
#Mann= 7 ,-1 , 0
  4780.2     .07       0  4863.8     .12       0    4992     .05       0
  5005.6     .12       0  5020.9     .07       0  5396.8     .12       0
    5501     .07       0
Bank Sta=4992,5005.6
XS Rating Curve= 0 ,0
Exp/Cntr=0.3,0.1

Type RM Length L Ch R = 1 ,32740   ,481,481,481
BEGIN DESCRIPTION:
SPRING CREEK_DS 58.0
END DESCRIPTION:
XS GIS Cut Line= 3
        2075575.     13857925.01      2075625.03     13857725.08
      2075224.99     13857124.99
#Sta/Elev= 30
  4793.9 1315.93  4832.2 1313.43  4876.4 1307.91  4927.9 1306.61  4948.5 1305.12
  4958.8 1302.33  4976.8 1292.62  4987.8 1291.76  4989.8 1291.42  4990.7 1289.32
  4991.2 1288.82  5004.3 1289.32  5013.6 1289.57  5043.6  1295.6  5121.8 1297.27
  5187.9  1300.2  5281.6 1302.75    5302 1304.29  5332.1 1303.22  5402.3 1304.19
  5476.8 1306.49  5523.1 1308.47  5533.4 1307.62  5548.4 1310.35  5569.5 1310.46
  5584.5 1312.54  5644.5 1316.96  5649.9 1317.66  5692.6 1321.97  5721.2 1322.37
#Mann= 11 ,-1 , 0
  4793.9     .12       0  4832.2     .07       0  4987.8     .12       0
  4990.7     .05       0  5004.3     .12       0  5281.6    .035       0
  5402.3     .07       0  5476.8    .035       0  5523.1     .07       0
  5644.5    .035       0  5649.9     .07       0
Bank Sta=4990.7,5004.3
XS Rating Curve= 0 ,0
Exp/Cntr=0.3,0.1

Type RM Length L Ch R = 1 ,32259   ,499,499,499
BEGIN DESCRIPTION:
SPRING CREEK_DS 57.0
END DESCRIPTION:
XS GIS Cut Line= 3
      2075724.99     13858225.02      2076075.01     13857632.59
        2076325.     13857025.01
#Sta/Elev= 30
  4311.9 1313.42    4467 1309.69  4520.4 1309.02  4579.3 1307.35  4655.3 1305.08
  4729.4 1300.25  4803.7 1298.76    4916 1295.95  4929.3  1296.1  4962.4  1289.7
  4983.9 1289.53  4984.4 1289.03  4997.6 1289.53    5008  1293.3  5026.4 1293.81
  5042.7 1293.93  5051.5 1297.95  5066.7 1298.55  5073.1 1295.84  5083.9 1294.92
  5090.6 1296.95  5114.6 1298.12  5200.1 1297.53    5306 1300.44  5321.8 1301.66
  5359.6 1308.84  5505.6 1315.74  5624.6 1329.65  5656.7 1331.67    5657 1331.67
#Mann= 13 ,-1 , 0
  4311.9    .035       0    4467     .07       0  4520.4    .035       0
  4579.3     .07       0  4803.7    .035       0    4916     .12       0
  4929.3    .035       0  4983.9    .035       0  4997.6    .035       0
  5026.4     .12       0  5200.1    .035       0    5306     .12       0
  5656.7     .07       0
Bank Sta=4983.9,4997.6
XS Rating Curve= 0 ,0
Exp/Cntr=0.3,0.1

Type RM Length L Ch R = 1 ,31760   ,565,565,565
BEGIN DESCRIPTION:
SPRING CREEK_DS 56.0
END DESCRIPTION:
XS GIS Cut Line= 3
      2075975.02     13858074.98      2076456.77     13857475.07
      2076525.01     13857274.98
#Sta/Elev= 30
  4230.6 1306.52  4266.6 1306.38  4308.2 1304.74    4337 1301.47  4351.4 1299.05
  4415.4 1296.83    4537 1297.96  4636.9  1295.1  4764.2 1293.04    4793 1293.77
  4828.2 1292.57  4898.6 1291.66  4942.2 1292.02    4972 1287.68    4985 1289.05
    4990 1287.01  4990.5 1286.51  5003.2 1286.51  5003.7 1287.01    5013 1289.28
  5021.2 1294.16    5039 1300.04  5054.6 1303.28  5070.4  1306.9  5095.2 1310.71
  5126.9 1317.01  5138.3 1320.06  5158.6 1322.96  5164.4 1324.52  5211.4 1328.62
#Mann= 7 ,-1 , 0
  4230.6     .07       0  4636.9    .035       0  4942.2     .07       0
    4972    .035       0    4990    .035       0  5003.7    .035       0
  5054.6     .07       0
Bank Sta=4990,5003.7
XS Rating Curve= 0 ,0
Exp/Cntr=0.3,0.1