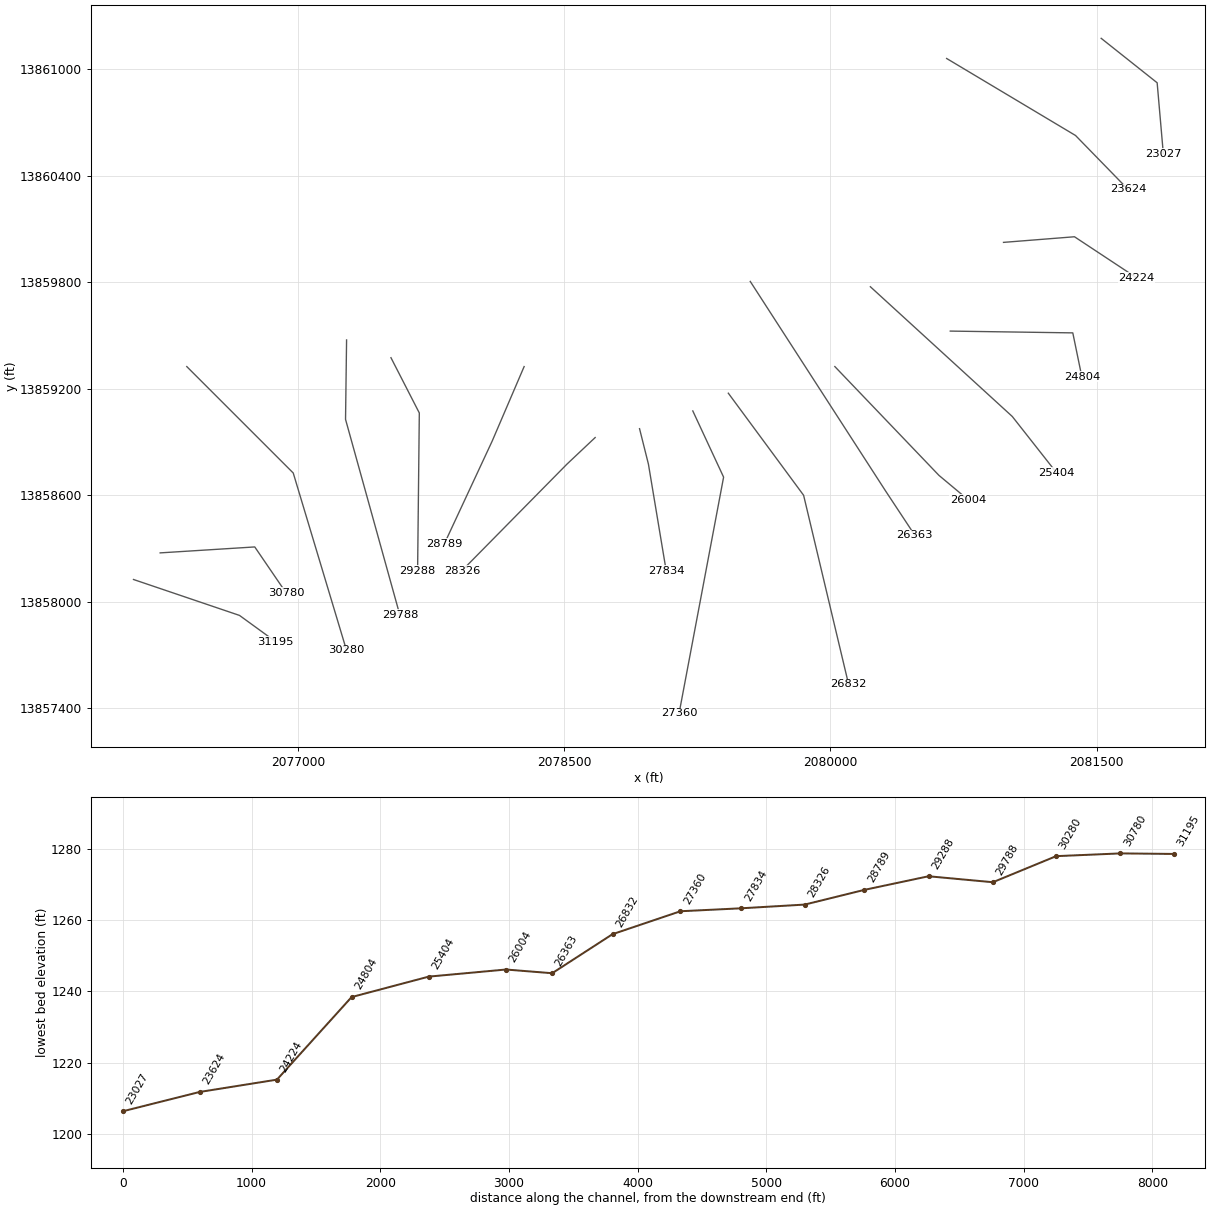
HEC-RAS study SPRING CREEK.prj: SPRING CREEK Base Level Engineering

--- SPRING CREEK.g01 (geometry) --- (continued)

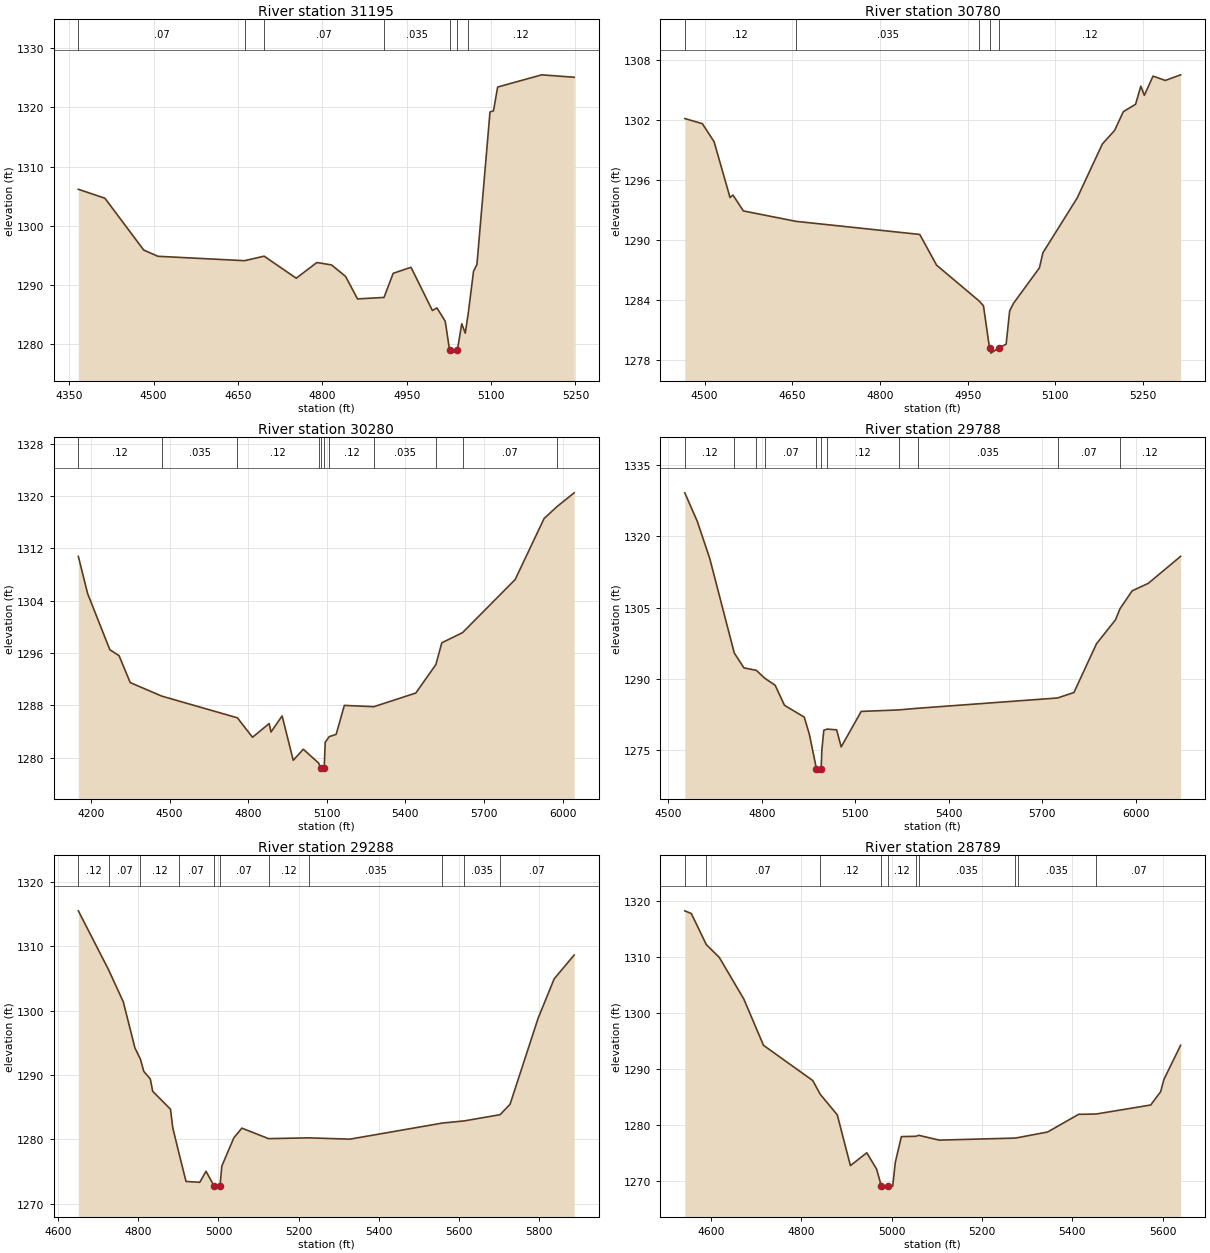
Type RM Length L Ch R = 1 ,31195   ,415,415,415
BEGIN DESCRIPTION:
SPRING CREEK_DS 55.0
END DESCRIPTION:
XS GIS Cut Line= 3
      2076074.96     13858125.02      2076671.97     13857922.55
        2076875.       13857775.
#Sta/Elev= 30
  4366.3 1306.19  4413.5 1304.68  4482.5 1295.94  4507.7 1294.88  4661.9 1294.14
  4696.6  1294.9  4753.7 1291.18  4790.3 1293.83  4816.5 1293.42  4841.5 1291.47
  4862.6 1287.69  4909.7 1287.94    4926 1292.01  4957.7 1293.02  4995.7 1285.73
  5003.8 1286.17  5018.5 1283.92  5026.3 1279.04  5026.8 1278.54  5040.1 1279.04
  5047.9  1283.5  5054.1 1281.91  5059.6 1285.36  5068.8 1292.34  5074.9 1293.51
  5098.1 1319.24  5104.3 1319.42  5111.7 1323.44  5190.1  1325.5  5247.7 1325.09
#Mann= 7 ,-1 , 0
  4366.3     .07       0  4661.9    .035       0  4696.6     .07       0
  4909.7    .035       0  5026.3    .035       0  5040.1    .035       0
  5059.6     .12       0
Bank Sta=5026.3,5040.1
XS Rating Curve= 0 ,0
Exp/Cntr=0.3,0.1

Type RM Length L Ch R = 1 ,30780   ,500,500,500
BEGIN DESCRIPTION:
SPRING CREEK_DS 54.0
END DESCRIPTION:
XS GIS Cut Line= 3
      2076225.05       13858275.      2076757.89     13858308.52
      2076935.03     13858048.77
#Sta/Elev= 30
  4466.1 1302.13  4496.1 1301.62  4516.2 1299.82  4543.5 1294.24  4548.5 1294.49
  4566.3  1292.9  4656.2 1291.86  4868.1 1290.55  4896.9 1287.48  4969.7  1283.9
  4977.1 1283.42  4987.1 1279.35  4989.1 1279.19  4989.6 1278.69  5002.9 1279.19
  5015.9 1279.59  5021.9 1282.91  5028.5 1283.67  5072.8 1287.21  5078.8 1288.72
  5137.4 1294.19  5180.5 1299.59  5201.5 1300.95  5216.4 1302.82  5237.4 1303.56
  5246.3 1305.37  5252.3 1304.45  5267.2 1306.37  5288.2 1305.94  5314.4  1306.5
#Mann= 5 ,-1 , 0
  4466.1     .12       0  4656.2    .035       0  4969.7     .12       0
  4989.1     .05       0  5002.9     .12       0
Bank Sta=4989.1,5002.9
XS Rating Curve= 0 ,0
Exp/Cntr=0.3,0.1

Type RM Length L Ch R = 1 ,30280   ,492,492,492
BEGIN DESCRIPTION:
SPRING CREEK_DS 53.0
END DESCRIPTION:
XS GIS Cut Line= 3
      2076375.02     13859324.98       2076974.6     13858725.17
        2077275.     13857725.01
#Sta/Elev= 30
  4151.9 1310.76  4187.2 1305.09  4272.1 1296.49  4307.4 1295.57  4349.9 1291.46
  4470.2 1289.39  4759.1 1286.07  4816.6  1283.1  4880.2 1285.19  4887.3  1283.9
  4929.7 1286.36  4972.1 1279.58  5010.6 1281.27  5069.3 1279.14  5076.3 1278.42
  5076.8 1277.92  5090.4 1278.42  5094.1 1282.32  5109.3 1283.19  5135.9 1283.54
  5167.2 1287.97  5279.7 1287.77  5439.9 1289.86  5516.5 1294.21  5539.1 1297.54
  5618.2 1299.09  5819.1 1307.21  5929.5 1316.54  5977.5 1318.32  6044.3 1320.47
#Mann= 11 ,-1 , 0
  4151.9     .12       0  4470.2    .035       0  4759.1     .12       0
  5069.3     .07       0  5076.3     .05       0  5090.4     .07       0
  5109.3     .12       0  5279.7    .035       0  5516.5     .12       0
  5618.2     .07       0  5977.5     .12       0
Bank Sta=5076.3,5090.4
XS Rating Curve= 0 ,0
Exp/Cntr=0.3,0.1

Type RM Length L Ch R = 1 ,29788   ,500,500,500
BEGIN DESCRIPTION:
SPRING CREEK_DS 52.0
END DESCRIPTION:
XS GIS Cut Line= 3
        2077275.     13859475.03      2077269.14     13859027.47
        2077575.     13857925.01
#Sta/Elev= 30
  4552.4 1329.12  4592.4 1323.14  4632.4 1315.34  4711.2 1295.45  4742.4 1292.31
    4782  1291.8  4809.1 1290.14  4842.5 1288.66  4872.5 1284.44  4935.9 1281.97
  4952.5  1278.3    4975 1271.11  4975.5 1270.61    4990 1271.11  4992.5 1275.13
  4998.7 1279.21  5009.8 1279.45  5039.8 1279.29  5054.4  1275.7  5118.7 1283.16
    5239 1283.48  5301.2 1283.83  5749.1 1285.99  5801.6 1287.14  5874.3 1297.42
  5934.9 1302.41  5949.4 1304.75  5988.4 1308.51  6040.3 1310.09  6144.1 1315.77
#Mann= 11 ,-1 , 0
  4552.4     .12       0  4711.2     .07       0    4782     .12       0
  4809.1     .07       0    4975     .05       0    4990     .07       0
  5009.8     .12       0    5239     .07       0  5301.2    .035       0
  5749.1     .07       0  5949.4     .12       0
Bank Sta=4975,4990
XS Rating Curve= 0 ,0
Exp/Cntr=0.3,0.1

Type RM Length L Ch R = 1 ,29288   ,499,499,499
BEGIN DESCRIPTION:
SPRING CREEK_DS 51.0
END DESCRIPTION:
XS GIS Cut Line= 3
      2077525.02     13859374.97      2077684.67     13859063.51
        2077675.     13858174.96
#Sta/Elev= 30
    4650 1315.49  4725.4 1306.36  4762.3 1301.36  4791.4  1294.2  4805.1 1292.46
  4813.6 1290.55  4829.8 1289.39  4835.8 1287.47  4880.2 1284.69  4885.9 1281.82
  4900.3 1278.13    4919 1273.47  4953.4 1273.34    4969 1275.06  4988.9 1272.78
  4989.4 1272.28  5003.9 1272.78  5008.5 1275.87  5038.5 1280.25  5058.5 1281.75
  5125.1 1280.12  5225.4 1280.24  5328.5 1280.04  5559.6 1282.54  5613.6 1282.87
  5703.6 1283.84  5728.5 1285.46  5798.6 1298.82  5838.6 1304.92  5888.6 1308.63
#Mann= 11 ,-1 , 0
    4650     .12       0  4725.4     .07       0  4805.1     .12       0
  4900.3     .07       0  4988.9     .05       0  5003.9     .07       0
  5125.1     .12       0  5225.4    .035       0  5559.6     .07       0
  5613.6    .035       0  5703.6     .07       0
Bank Sta=4988.9,5003.9
XS Rating Curve= 0 ,0
Exp/Cntr=0.3,0.1

Type RM Length L Ch R = 1 ,28789   ,463,463,463
BEGIN DESCRIPTION:
SPRING CREEK_DS 50.0
END DESCRIPTION:
XS GIS Cut Line= 3
        2078275.       13859325.      2078094.83     13858904.58
      2077825.01     13858325.01
#Sta/Elev= 30
  4542.6 1318.31  4557.1 1317.82  4590.2 1312.26  4618.8 1309.98  4673.2  1302.5
  4716.7 1294.22  4825.5 1287.92  4842.3 1285.44  4879.9 1281.76  4908.9 1272.67
  4945.1 1274.97  4966.9 1272.04  4977.5 1268.96    4978 1268.46  4992.6 1268.96
  5002.5    1269  5008.2 1273.24  5021.6 1277.87  5053.3 1277.92  5060.1  1278.1
  5105.3 1277.24  5272.2  1277.6  5280.4  1277.7  5345.1 1278.69  5413.7 1281.86
  5452.2 1281.91  5573.1 1283.53  5595.2 1285.92  5602.2 1288.08  5639.3 1294.23
#Mann= 10 ,-1 , 0
  4542.6    .035       0  4590.2     .07       0  4842.3     .12       0
  4977.5     .05       0  4992.6     .12       0  5053.3     .07       0
  5060.1    .035       0  5272.2     .07       0  5280.4    .035       0
  5452.2     .07       0
Bank Sta=4977.5,4992.6
XS Rating Curve= 0 ,0
Exp/Cntr=0.3,0.1

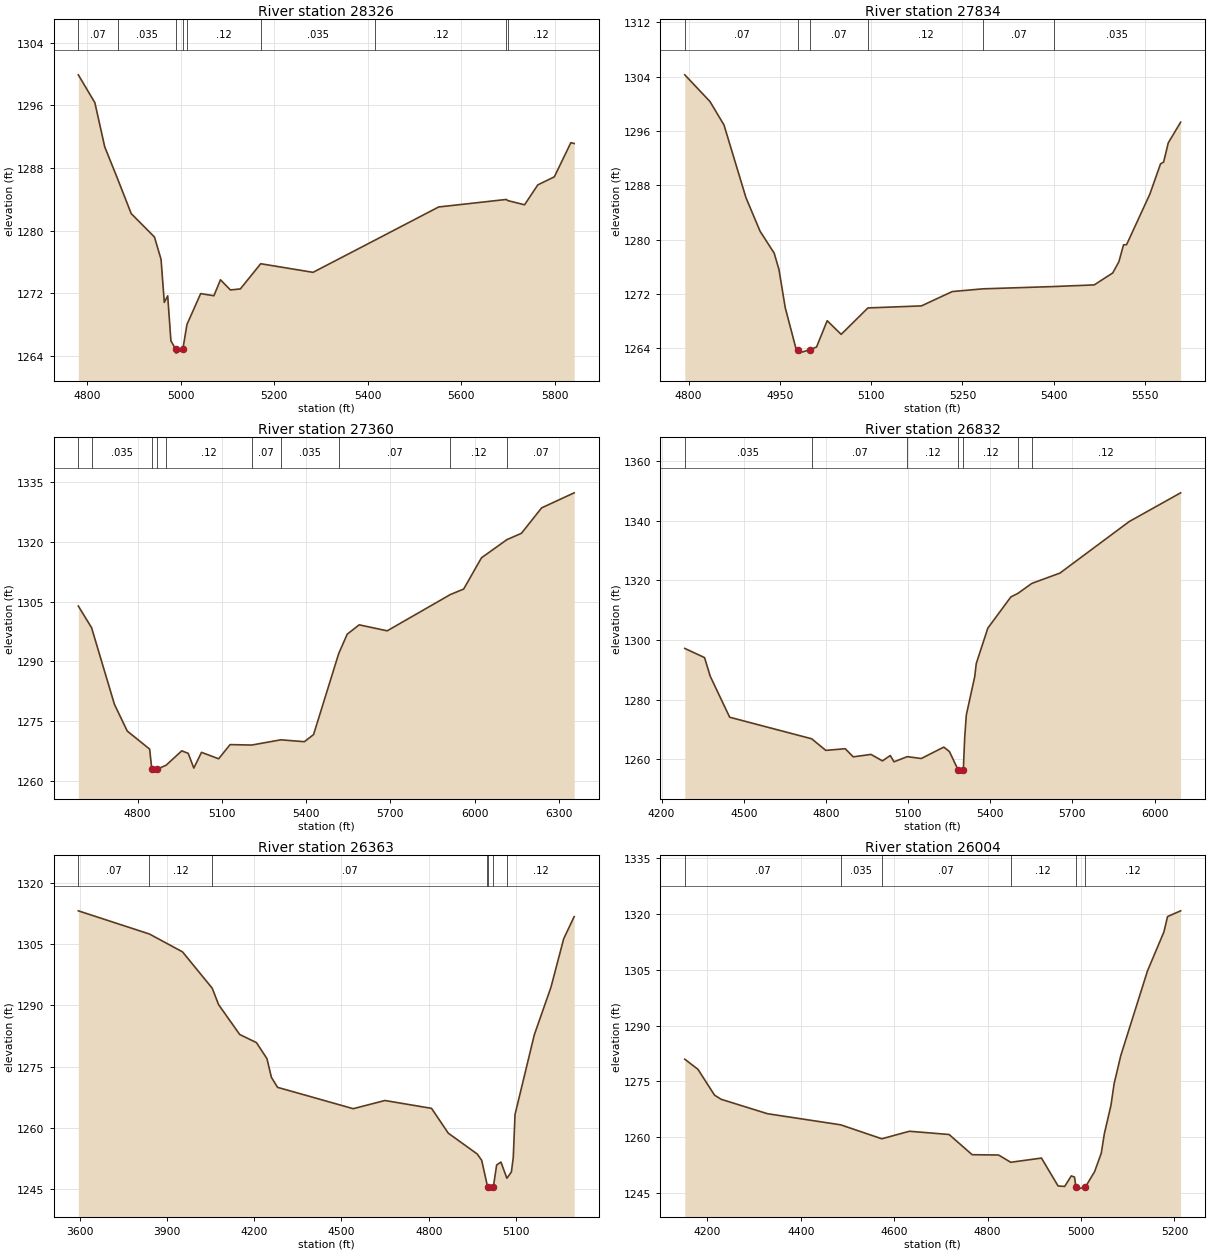
Type RM Length L Ch R = 1 ,28326   ,492,492,492
BEGIN DESCRIPTION:
SPRING CREEK_DS 49.0
END DESCRIPTION:
XS GIS Cut Line= 3
      2078675.02     13858925.02      2078515.86     13858774.88
        2077925.       13858175.
#Sta/Elev= 30
  4781.2 1299.89  4816.6 1296.33  4837.7 1290.69  4865.4 1286.58  4894.3 1282.17
  4944.1 1279.17  4958.2 1276.31  4965.1 1270.82  4972.4 1271.66  4979.3  1265.9
  4989.6 1264.84  4990.1 1264.34  5004.8 1264.84  5013.6    1268  5042.9 1271.94
  5071.2 1271.67  5085.3 1273.71  5106.6 1272.41  5127.8 1272.54  5171.4 1275.76
  5283.3 1274.66  5416.8  1278.8  5552.1 1283.01  5696.7 1283.97  5700.4 1283.82
  5735.9 1283.29  5764.2 1285.83  5799.6 1286.86  5834.9 1291.22    5842 1291.12
#Mann= 9 ,-1 , 0
  4781.2     .07       0  4865.4    .035       0  4989.6    .035       0
  5004.8    .035       0  5013.6     .12       0  5171.4    .035       0
  5416.8     .12       0  5696.7     .07       0  5700.4     .12       0
Bank Sta=4989.6,5004.8
XS Rating Curve= 0 ,0
Exp/Cntr=0.3,0.1

Type RM Length L Ch R = 1 ,27834   ,474,474,474
BEGIN DESCRIPTION:
SPRING CREEK_DS 48.0
END DESCRIPTION:
XS GIS Cut Line= 3
      2078924.99     13858975.04      2078975.05     13858775.11
        2079075.     13858174.98
#Sta/Elev= 30
  4793.9 1304.25  4835.2 1300.33  4858.3 1296.87  4894.4 1286.17  4917.6 1281.23
  4940.7 1278.02  4948.6  1275.6  4958.9 1269.99  4976.8 1263.88  4980.1  1263.8
  4980.6  1263.3  4999.6  1263.8  5010.3  1264.2  5027.8 1268.07  5050.8 1266.06
  5094.7 1269.95  5182.6 1270.25  5233.3 1272.36  5283.5 1272.76  5400.8  1273.1
  5466.5 1273.34  5496.9  1275.1    5507 1276.75  5514.6 1279.23  5519.6 1279.26
  5557.7 1286.66  5575.4 1291.15  5580.5 1291.42  5588.1 1294.24  5608.4 1297.28
#Mann= 6 ,-1 , 0
  4793.9     .07       0  4980.1     .05       0  4999.6     .07       0
  5094.7     .12       0  5283.5     .07       0  5400.8    .035       0
Bank Sta=4980.1,4999.6
XS Rating Curve= 0 ,0
Exp/Cntr=0.3,0.1

Type RM Length L Ch R = 1 ,27360   ,528,528,528
BEGIN DESCRIPTION:
SPRING CREEK_DS 47.0
END DESCRIPTION:
XS GIS Cut Line= 3
        2079225.       13859075.      2079398.44     13858701.95
      2079147.66     13857370.46
#Sta/Elev= 30
  4588.6 1303.86  4635.8 1298.43  4717.2 1279.22    4763 1272.51  4842.7 1267.99
  4850.3 1262.97  4850.8 1262.47  4869.8 1262.97  4901.4 1263.96  4957.1 1267.56
    4980 1266.93    5000 1263.24  5027.4 1267.18  5088.5 1265.57  5129.2 1269.12
  5206.5 1269.01  5309.9 1270.32  5393.8 1269.85  5426.6 1271.64  5516.3 1291.98
  5546.4  1296.8    5589 1299.15  5688.9 1297.65  5914.2 1306.76  5961.3 1308.12
  6024.7 1315.96  6115.6 1320.52  6167.1  1322.1  6238.8 1328.47  6354.9 1332.25
#Mann= 10 ,-1 , 0
  4588.6     .07       0  4635.8    .035       0  4850.3     .05       0
  4869.8    .035       0  4901.4     .12       0  5206.5     .07       0
  5309.9    .035       0  5516.3     .07       0  5914.2     .12       0
  6115.6     .07       0
Bank Sta=4850.3,4869.8
XS Rating Curve= 0 ,0
Exp/Cntr=0.3,0.1

Type RM Length L Ch R = 1 ,26832   ,469,469,469
BEGIN DESCRIPTION:
SPRING CREEK_DS 46.0
END DESCRIPTION:
XS GIS Cut Line= 3
      2079425.01     13859174.98      2079849.05     13858599.63
      2080102.52     13857533.68
#Sta/Elev= 30
  4284.7 1297.21  4356.8 1294.13  4377.6 1287.87  4448.6 1274.12  4748.1 1266.89
  4799.5    1263  4870.5 1263.56  4899.7 1260.83  4964.5 1261.65  5006.4 1259.48
    5035 1261.28  5048.6 1259.17    5097  1260.9  5148.1 1260.27  5230.3  1264.1
  5250.9 1262.62  5282.2 1256.54  5282.7 1256.04  5301.7 1256.54  5306.8 1267.45
  5312.6 1274.88  5343.4 1287.78  5348.9 1292.13  5391.1 1304.01  5475.4  1314.5
  5500.9 1315.67  5551.8 1319.02  5654.4 1322.48  5907.4 1339.77  6095.1 1349.41
#Mann= 7 ,-1 , 0
  4284.7    .035       0  4748.1     .07       0    5097     .12       0
  5282.2     .05       0  5301.7     .12       0  5500.9     .07       0
  5551.8     .12       0
Bank Sta=5282.2,5301.7
XS Rating Curve= 0 ,0
Exp/Cntr=0.3,0.1

Type RM Length L Ch R = 1 ,26363   ,359,359,359
BEGIN DESCRIPTION:
SPRING CREEK_DS 45.0
END DESCRIPTION:
XS GIS Cut Line= 3
      2079548.57      13859804.9      2080310.02     13858624.96
        2080475.       13858375.
#Sta/Elev= 30
  3595.7 1313.14    3840 1307.47  3953.7 1303.11  4055.9 1294.21  4077.7  1290.2
  4150.3  1282.9  4207.7 1280.92  4243.8    1277  4259.2 1272.42  4280.3 1269.98
  4540.3 1264.76  4649.2 1266.76  4809.5 1264.84    4867 1258.77  4966.6 1253.67
  4981.8 1252.12  5001.1 1245.96    5002 1245.59  5002.5 1245.09  5021.8 1245.59
  5033.1 1250.99  5047.9 1251.71  5068.3 1247.75  5083.8 1249.28  5090.3 1252.84
  5096.3 1263.34  5162.5 1282.81  5219.7 1294.44  5263.6 1306.32  5299.5 1311.72
#Mann= 7 ,-1 , 0
  3595.7     .07       0    3840     .12       0  4055.9     .07       0
  5001.1    .035       0    5002     .05       0  5021.8    .035       0
  5068.3     .12       0
Bank Sta=5002,5021.8
XS Rating Curve= 0 ,0
Exp/Cntr=0.3,0.1

Type RM Length L Ch R = 1 ,26004   ,600,600,600
BEGIN DESCRIPTION:
SPRING CREEK_DS 44.0
END DESCRIPTION:
XS GIS Cut Line= 3
      2080024.98     13859325.03      2080611.37     13858711.76
      2080775.03     13858574.97
#Sta/Elev= 30
  4151.5 1280.97  4179.7 1278.26  4215.2 1271.33  4229.4 1270.22  4328.4 1266.36
  4485.5 1263.37  4573.4 1259.63  4632.6 1261.65  4717.5 1260.78  4766.9 1255.36
  4823.5 1255.28  4849.5 1253.33  4915.3 1254.46  4950.9 1246.98    4965 1246.85
  4979.2 1249.68  4986.1 1249.36  4989.1 1246.63  4989.6 1246.13    5009 1246.63
  5029.1 1250.82  5043.4 1255.77  5049.9 1260.95  5064.2 1268.66  5070.8 1274.35
  5085.1 1281.92  5142.3 1304.64  5177.5 1315.09  5185.3 1319.22  5213.3 1320.76
#Mann= 6 ,-1 , 0
  4151.5     .07       0  4485.5    .035       0  4573.4     .07       0
  4849.5     .12       0  4989.1     .05       0    5009     .12       0
Bank Sta=4989.1,5009
XS Rating Curve= 0 ,0
Exp/Cntr=0.3,0.1

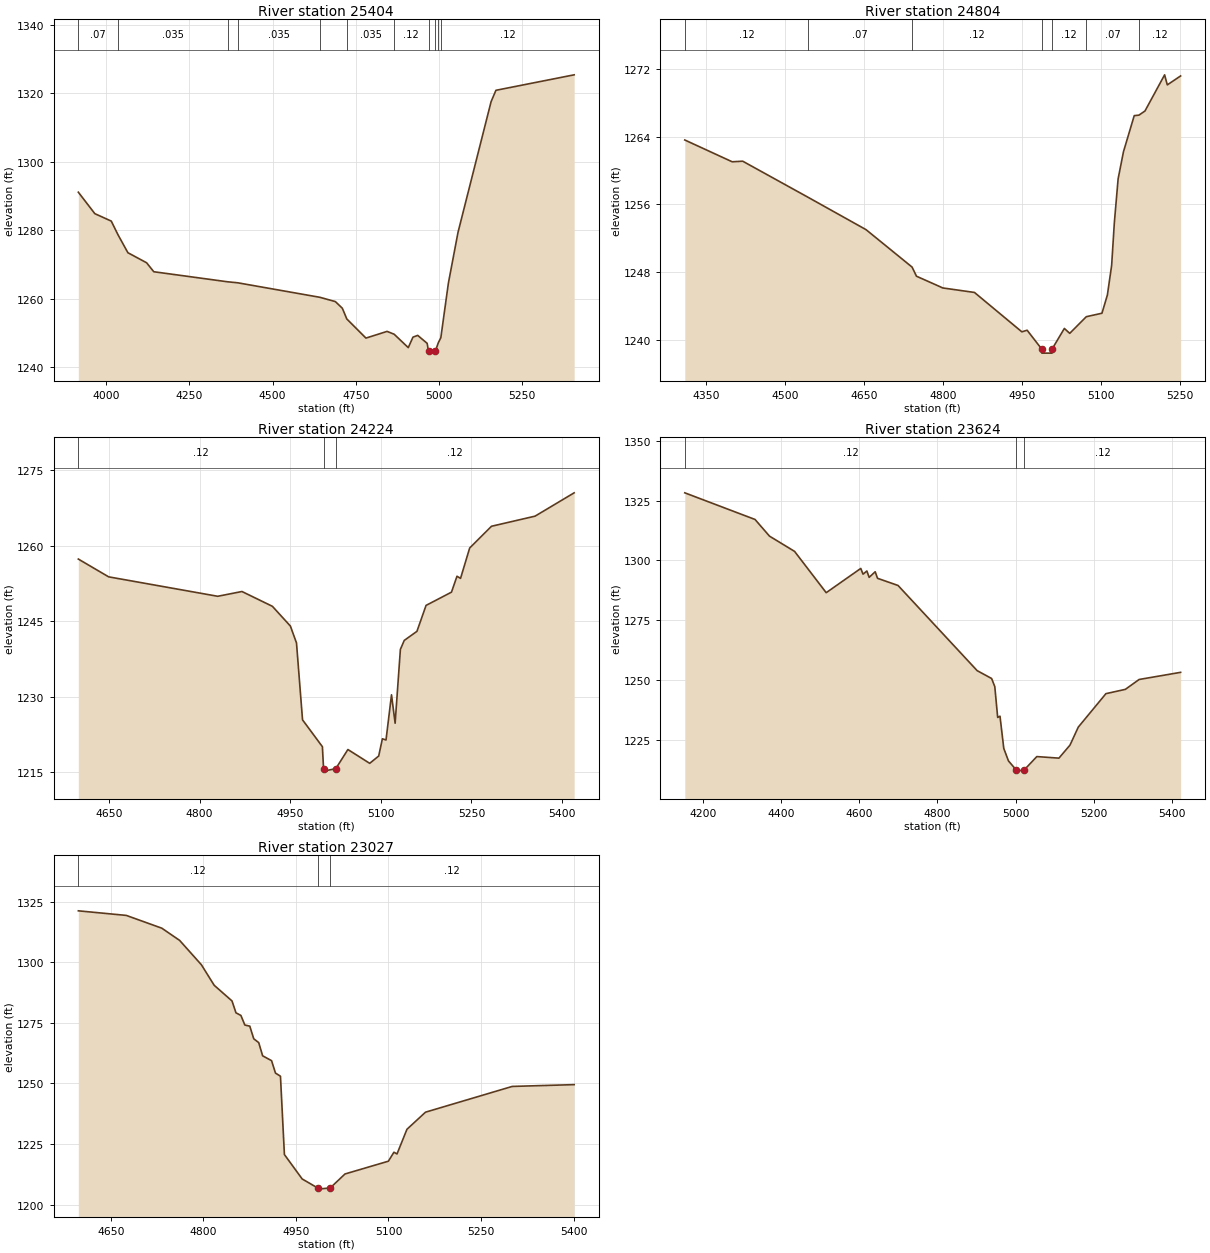
Type RM Length L Ch R = 1 ,25404   ,600,600,600
BEGIN DESCRIPTION:
SPRING CREEK_DS 43.0
END DESCRIPTION:
XS GIS Cut Line= 3
      2080225.02     13859774.98       2081024.3     13859043.76
      2081274.98     13858725.03
#Sta/Elev= 30
  3916.7 1291.14  3966.3 1284.87  4015.6  1282.7  4035.7 1278.73  4065.6 1273.46
  4121.7 1270.53  4143.3 1267.91  4365.2 1264.97  4395.4 1264.68  4642.2 1260.44
  4688.5 1259.19  4709.4 1257.25  4722.9 1254.11  4780.3 1248.53  4843.8 1250.49
    4865 1249.66  4907.4 1245.75  4921.5 1248.81  4935.7 1249.32  4964.1    1247
  4968.3 1244.64  4968.8 1244.14  4988.3 1244.64  4997.8 1247.21  5005.2 1248.65
  5027.8 1264.55  5056.7 1279.39  5156.1 1317.59  5170.6  1320.9  5405.5 1325.42
#Mann= 11 ,-1 , 0
  3916.7     .07       0  4035.7    .035       0  4365.2     .12       0
  4395.4    .035       0  4642.2     .12       0  4722.9    .035       0
    4865     .12       0  4968.3     .05       0  4988.3     .12       0
  4997.8     .07       0  5005.2     .12       0
Bank Sta=4968.3,4988.3
XS Rating Curve= 0 ,0
Exp/Cntr=0.3,0.1

Type RM Length L Ch R = 1 ,24804   ,580,580,580
BEGIN DESCRIPTION:
SPRING CREEK_DS 42.0
END DESCRIPTION:
XS GIS Cut Line= 3
        2080675.       13859525.      2081365.12     13859514.95
      2081415.82     13859268.71
#Sta/Elev= 30
  4309.8 1263.62  4399.8 1261.04  4419.8 1261.11  4544.2 1256.83    4654 1253.01
  4741.4 1248.58  4749.8  1247.5  4799.9 1246.11  4859.9 1245.58  4949.9 1240.92
  4959.9 1241.11  4987.4  1238.9  4987.9  1238.4    5007  1238.4  5007.5  1238.9
  5030.6 1241.32  5040.8 1240.74  5072.3 1242.71    5102 1243.12  5112.3 1245.27
  5120.4 1248.78  5125.5 1253.81  5132.7 1259.02  5142.9 1262.24  5163.3  1266.5
  5172.2 1266.56  5183.7 1267.05    5221 1271.33  5226.1 1270.14  5251.4  1271.2
#Mann= 7 ,-1 , 0
  4309.8     .12       0  4544.2     .07       0  4741.4     .12       0
  4987.4     .05       0  5007.5     .12       0  5072.3     .07       0
  5172.2     .12       0
Bank Sta=4987.4,5007.5
XS Rating Curve= 0 ,0
Exp/Cntr=0.3,0.1

Type RM Length L Ch R = 1 ,24224   ,600,600,600
BEGIN DESCRIPTION:
SPRING CREEK_DS 41.0
END DESCRIPTION:
XS GIS Cut Line= 3
      2080974.96       13860025.      2081374.61     13860056.66
      2081724.96     13859825.03
#Sta/Elev= 30
  4599.1 1257.35  4649.3 1253.82  4829.9 1249.96    4870 1250.91  4920.4 1247.97
  4950.2 1244.05  4960.3  1240.7  4970.3 1225.43  5003.2  1220.1  5005.1 1215.75
  5005.6 1215.25  5025.4 1215.75  5045.4 1219.54  5081.5  1216.8  5096.4 1218.25
  5102.5 1221.67  5108.5 1221.43  5117.6  1230.4  5123.6 1224.76  5132.3 1239.42
  5138.7  1241.2  5159.7    1243  5174.8 1248.15  5216.9 1250.78    5226 1253.94
  5231.9 1253.52    5247 1259.54  5283.1 1263.86  5355.3 1265.87    5420  1270.5
#Mann= 3 ,-1 , 0
  4599.1     .12       0  5005.1     .05       0  5025.4     .12       0
Bank Sta=5005.1,5025.4
XS Rating Curve= 0 ,0
Exp/Cntr=0.3,0.1

Type RM Length L Ch R = 1 ,23624   ,597,597,597
BEGIN DESCRIPTION:
SPRING CREEK_DS 40.0
END DESCRIPTION:
XS GIS Cut Line= 3
      2080654.63     13861061.43      2081380.65     13860627.32
      2081675.03     13860324.97
#Sta/Elev= 30
  4154.1 1328.29  4333.7 1317.14  4370.7 1310.16  4434.8 1303.78  4515.7 1286.49
  4604.1 1296.64  4609.9 1294.24  4619.7 1295.57  4625.5 1292.91    4641 1295.26
  4646.9 1292.51  4699.4 1289.51  4901.7 1253.86  4938.7 1250.57  4946.8 1247.18
  4954.2 1234.26  4960.1 1234.81  4969.8 1221.31  4981.8 1216.07  5001.6  1212.3
  5002.1  1211.8    5022  1212.3  5054.3 1217.89  5110.8 1217.23  5139.1 1222.69
  5160.3 1230.22    5231 1244.23  5280.6 1246.02  5315.9 1250.16    5422 1253.15
#Mann= 3 ,-1 , 0
  4154.1     .12       0  5001.6     .05       0    5022     .12       0
Bank Sta=5001.6,5022
XS Rating Curve= 0 ,0
Exp/Cntr=0.3,0.1

Type RM Length L Ch R = 1 ,23027   ,598,598,598
BEGIN DESCRIPTION:
SPRING CREEK_DS 39.0
END DESCRIPTION:
XS GIS Cut Line= 3
      2081525.02     13861174.98      2081840.22     13860924.51
        2081875.     13860525.02
#Sta/Elev= 30
  4597.4 1321.18  4675.1 1319.29  4732.7 1314.02  4761.6 1308.98  4796.8 1298.95
  4817.6 1290.47  4846.5    1284  4852.9 1279.12  4860.9 1278.02  4867.3 1274.07
  4875.3 1273.61  4881.7 1268.41  4889.8 1266.81  4896.1 1261.38  4910.6 1259.38
  4916.9 1254.26    4925 1252.96  4931.4 1220.65  4960.2 1210.58  4985.2 1206.89
  4985.7 1206.39  5005.7 1206.89  5029.6 1212.64  5099.9 1217.91  5108.9 1221.61
  5113.9  1220.9    5130 1231.07  5160.1 1238.13  5300.6 1248.75    5401 1249.49
#Mann= 3 ,-1 , 0
  4597.4     .12       0  4985.2     .05       0  5005.7     .12       0
Bank Sta=4985.2,5005.7
XS Rating Curve= 0 ,0
Exp/Cntr=0.3,0.1