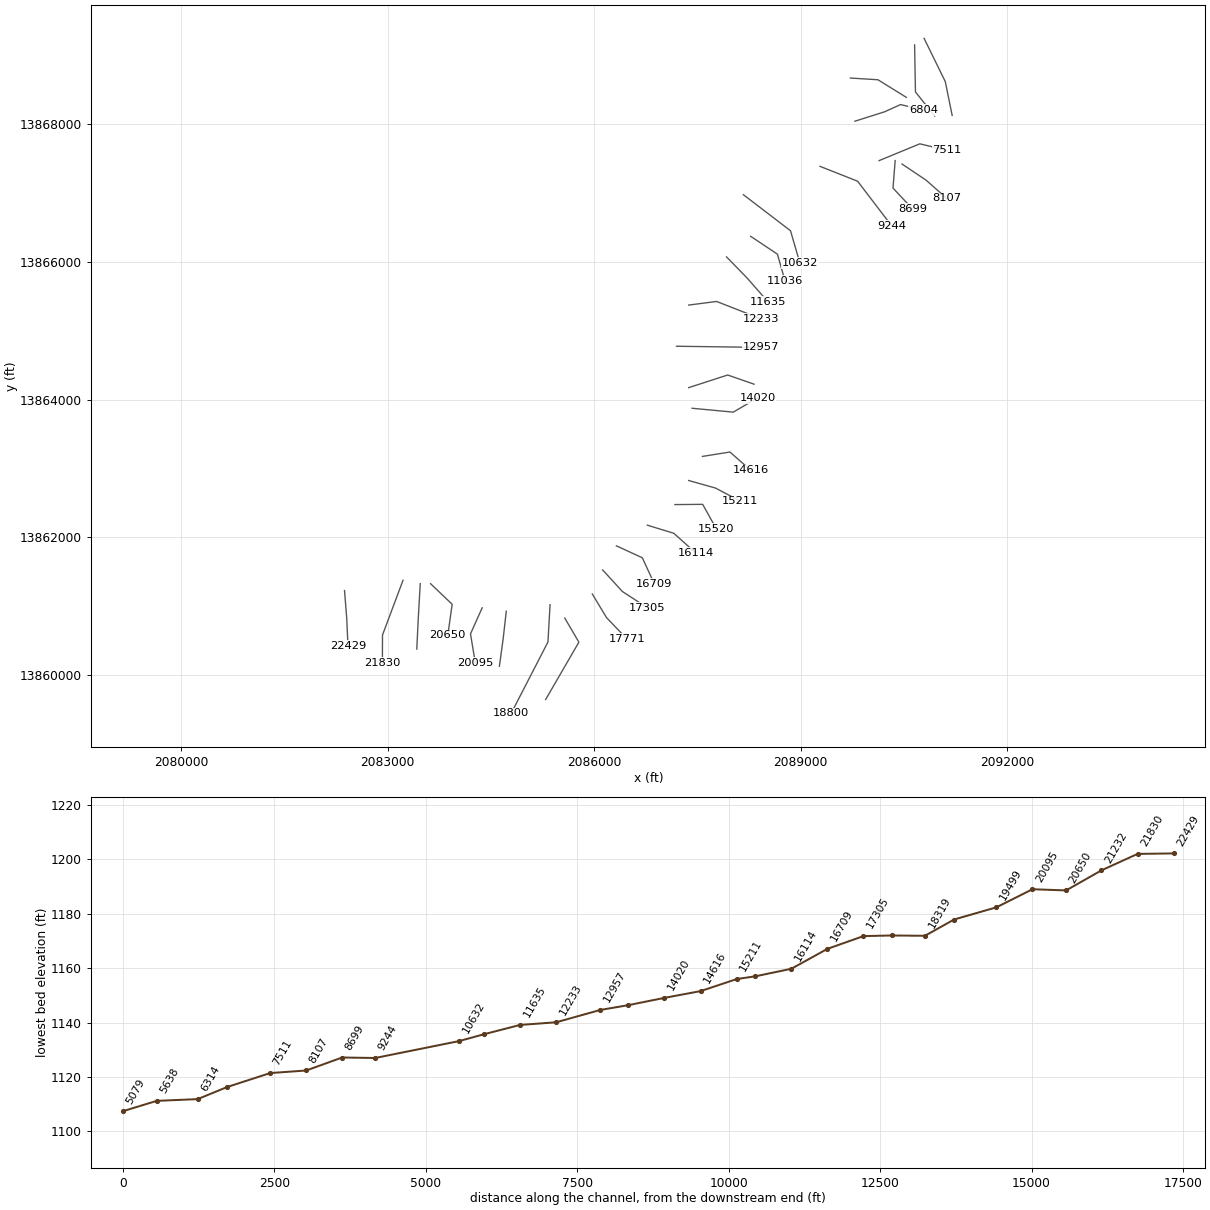
HEC-RAS study SPRING CREEK.prj: SPRING CREEK Base Level Engineering

--- SPRING CREEK.g01 (geometry) --- (continued)

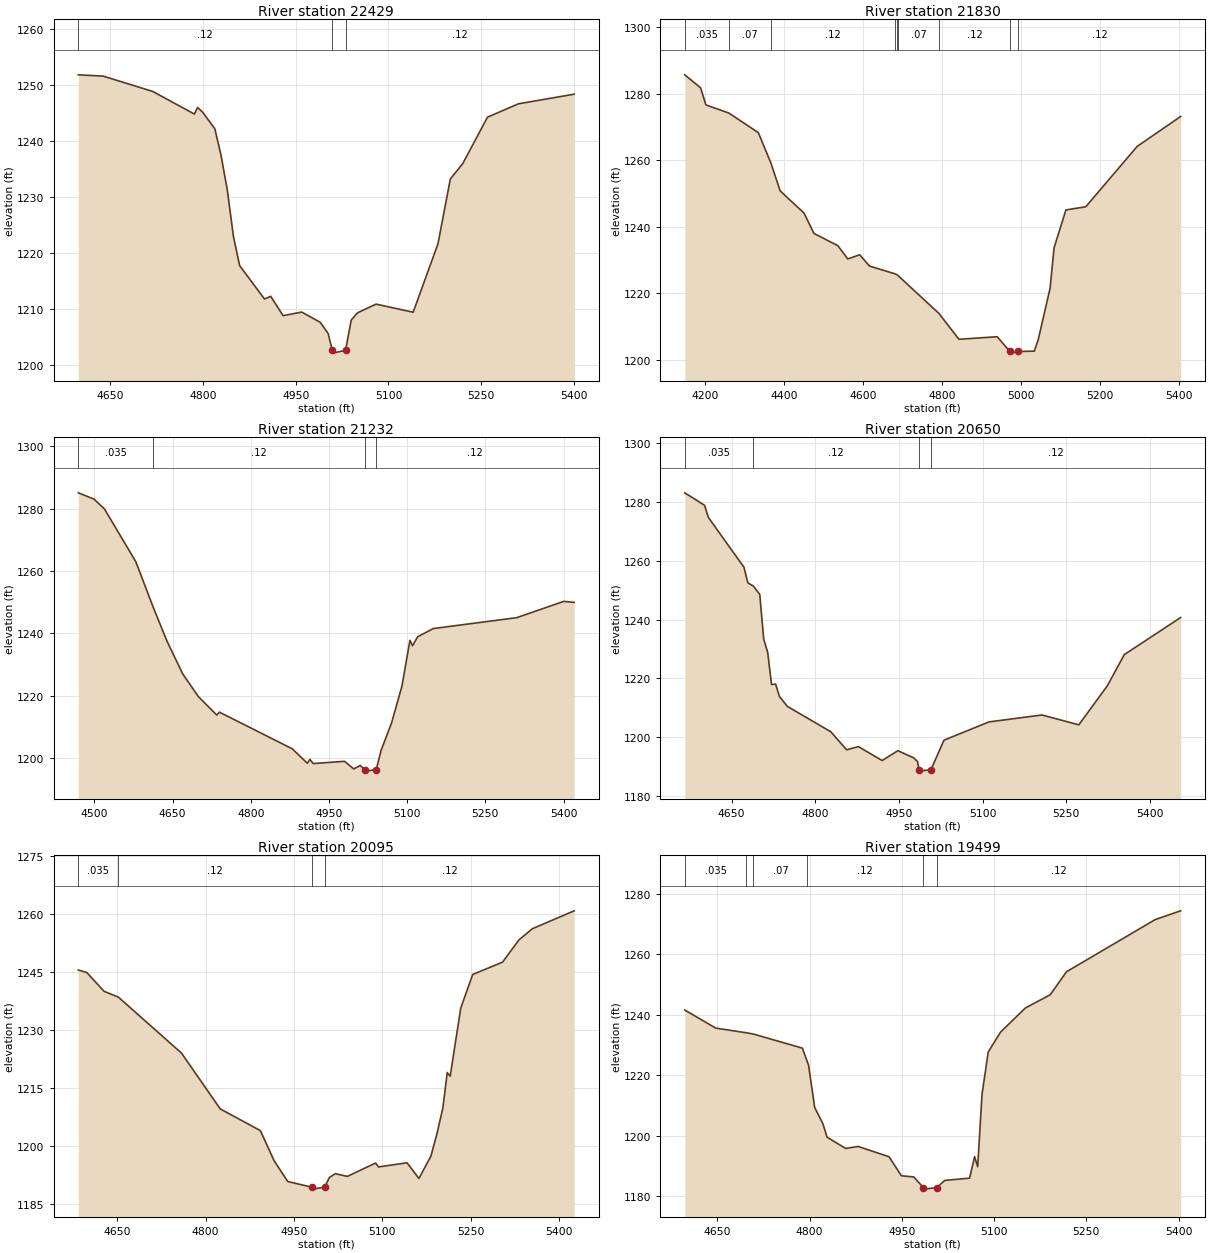
Type RM Length L Ch R = 1 ,22429   ,599,599,599
BEGIN DESCRIPTION:
SPRING CREEK_DS 38.0
END DESCRIPTION:
XS GIS Cut Line= 3
        2082375.     13861225.03      2082406.73     13860824.78
        2082425.       13860425.
#Sta/Elev= 30
  4598.5 1251.75  4638.7 1251.52  4718.9 1248.78  4786.2 1244.75  4791.2 1245.93
  4799.2 1245.13  4819.2 1242.15  4829.2 1237.42  4839.3 1231.27  4849.3 1222.93
  4859.3 1217.74  4899.5 1211.78  4909.5 1212.26  4929.6 1208.81  4959.7 1209.45
  4989.7 1207.62  5002.4 1205.63  5009.2 1202.63  5009.7 1202.13  5030.5 1202.63
  5039.8 1208.03  5049.8 1209.31  5079.9 1210.87  5139.9 1209.42    5180 1221.62
    5200 1233.18    5220 1235.91  5260.1  1244.2  5310.1 1246.58  5400.2  1248.3
#Mann= 3 ,-1 , 0
  4598.5     .12       0  5009.2     .05       0  5030.5     .12       0
Bank Sta=5009.2,5030.5
XS Rating Curve= 0 ,0
Exp/Cntr=0.3,0.1

Type RM Length L Ch R = 1 ,21830   ,598,598,598
BEGIN DESCRIPTION:
SPRING CREEK_DS 37.0
END DESCRIPTION:
XS GIS Cut Line= 3
      2083224.98     13861374.96      2082926.55     13860578.75
        2082925.     13860174.95
#Sta/Elev= 30
  4149.7 1285.74  4189.7 1281.82  4203.1 1276.68    4261 1274.24  4335.7 1268.34
  4367.3 1259.24  4390.9  1250.8  4451.4 1244.09  4476.3 1237.99  4536.9  1234.3
  4561.8 1230.31  4592.1 1231.56    4617 1228.16  4681.1 1225.84  4686.2 1225.58
  4689.4 1225.26  4792.5  1213.9  4843.1 1206.12  4939.9 1206.89  4971.9 1202.45
  4972.4 1201.95  4993.3 1202.45  5033.7 1202.54  5043.7 1206.02  5073.7 1221.53
  5083.7 1233.65  5113.7 1245.07  5163.8    1246  5293.8 1264.18  5403.8 1273.19
#Mann= 9 ,-1 , 0
  4149.7    .035       0    4261     .07       0  4367.3     .12       0
  4681.1     .07       0  4686.2     .12       0  4689.4     .07       0
  4792.5     .12       0  4971.9     .05       0  4993.3     .12       0
Bank Sta=4971.9,4993.3
XS Rating Curve= 0 ,0
Exp/Cntr=0.3,0.1

Type RM Length L Ch R = 1 ,21232   ,582,582,582
BEGIN DESCRIPTION:
SPRING CREEK_DS 36.0
END DESCRIPTION:
XS GIS Cut Line= 3
        2083475.     13861324.98      2083445.03     13860794.93
        2083425.       13860375.
#Sta/Elev= 30
  4469.1 1285.02  4499.1 1283.02  4519.2 1279.86  4579.3    1263  4613.3 1248.16
  4639.4 1237.45  4669.4 1227.02  4699.4 1219.77  4734.7 1213.85  4739.7 1214.78
  4879.7 1203.03  4908.4 1198.42  4913.4 1199.65  4919.8 1198.31  4979.9 1199.03
  4997.5  1196.6  5009.9 1197.69  5019.2 1196.39  5019.7 1195.89  5040.7 1196.39
    5050 1202.55    5070 1211.28    5090 1223.11  5105.3 1237.78  5110.3 1236.04
  5120.1 1238.92  5150.1 1241.55  5310.3 1245.04  5400.4 1250.26  5420.4 1249.94
#Mann= 4 ,-1 , 0
  4469.1    .035       0  4613.3     .12       0  5019.2     .05       0
  5040.7     .12       0
Bank Sta=5019.2,5040.7
XS Rating Curve= 0 ,0
Exp/Cntr=0.3,0.1

Type RM Length L Ch R = 1 ,20650   ,555,555,555
BEGIN DESCRIPTION:
SPRING CREEK_DS 35.0
END DESCRIPTION:
XS GIS Cut Line= 3
      2083625.01     13861324.99      2083938.84      13861025.5
        2083875.       13860575.
#Sta/Elev= 30
  4566.2 1283.05  4601.6 1278.81  4608.5 1274.69  4672.3 1257.77  4679.2 1252.48
  4689.1  1251.4  4700.6 1248.54  4707.6 1233.41  4714.8 1228.86  4721.7 1217.96
  4728.9  1218.1  4735.9 1213.87    4750 1210.53    4828 1201.89  4856.3 1195.77
  4877.4 1196.86  4919.9 1192.13  4948.2 1195.47  4976.5 1193.04  4983.4 1191.79
    4986 1189.03  4986.5 1188.53  5007.5 1189.03  5030.8 1199.04  5111.6 1205.25
  5206.6  1207.6  5272.5 1204.25  5323.7 1217.53    5354  1228.1    5455 1240.69
#Mann= 4 ,-1 , 0
  4566.2    .035       0  4689.1     .12       0    4986     .05       0
  5007.5     .12       0
Bank Sta=4986,5007.5
XS Rating Curve= 0 ,0
Exp/Cntr=0.3,0.1

Type RM Length L Ch R = 1 ,20095   ,596,596,596
BEGIN DESCRIPTION:
SPRING CREEK_DS 34.0
END DESCRIPTION:
XS GIS Cut Line= 3
      2084374.98     13860974.97      2084205.07     13860595.03
        2084275.     13860175.01
#Sta/Elev= 30
  4583.8 1245.59  4598.1 1244.95  4627.6 1240.08  4651.7  1238.6    4759 1224.12
  4824.8  1209.7    4893 1204.09  4916.2 1196.33  4939.4 1190.94  4980.4 1189.47
  4980.9 1188.97  5002.1 1189.47  5010.2 1191.99  5020.3 1192.96  5040.6 1192.26
  5088.6 1195.71  5093.6 1194.71    5142 1195.77  5162.2 1191.72  5182.5 1197.48
  5192.6 1203.17  5202.8 1209.91  5210.3 1219.09  5215.3 1218.15  5233.2 1235.75
  5253.5 1244.44  5304.2 1247.63    5332 1253.37  5354.8 1256.26  5425.8 1260.89
#Mann= 4 ,-1 , 0
  4583.8    .035       0  4651.7     .12       0  4980.4     .05       0
  5002.1     .12       0
Bank Sta=4980.4,5002.1
XS Rating Curve= 0 ,0
Exp/Cntr=0.3,0.1

Type RM Length L Ch R = 1 ,19499   ,699,699,699
BEGIN DESCRIPTION:
SPRING CREEK_DS 33.0
END DESCRIPTION:
XS GIS Cut Line= 3
        2084725.     13860924.97       2084679.7     13860524.63
      2084624.99     13860124.95
#Sta/Elev= 30
  4597.1 1241.54  4647.4 1235.56  4696.8 1234.03  4708.7 1233.59  4788.3 1228.94
  4796.2 1224.52  4798.3 1223.34  4808.4 1209.26  4821.5 1204.03  4828.5 1199.49
  4858.7 1195.77  4878.9 1196.43  4929.2 1193.03  4949.3 1186.74  4969.4 1186.35
  4985.1 1182.82  4985.6 1182.32  5006.8 1182.82  5019.8  1185.2  5060.2 1185.95
  5068.4 1193.04  5073.4 1189.74  5080.4 1213.57  5090.5 1227.64  5110.6 1234.25
    5151 1242.22  5191.4  1246.6  5217.8 1254.19  5362.2 1271.46  5403.4 1274.34
#Mann= 6 ,-1 , 0
  4597.1    .035       0  4696.8     .12       0  4708.7     .07       0
  4796.2     .12       0  4985.1     .05       0  5006.8     .12       0
Bank Sta=4985.1,5006.8
XS Rating Curve= 0 ,0
Exp/Cntr=0.3,0.1

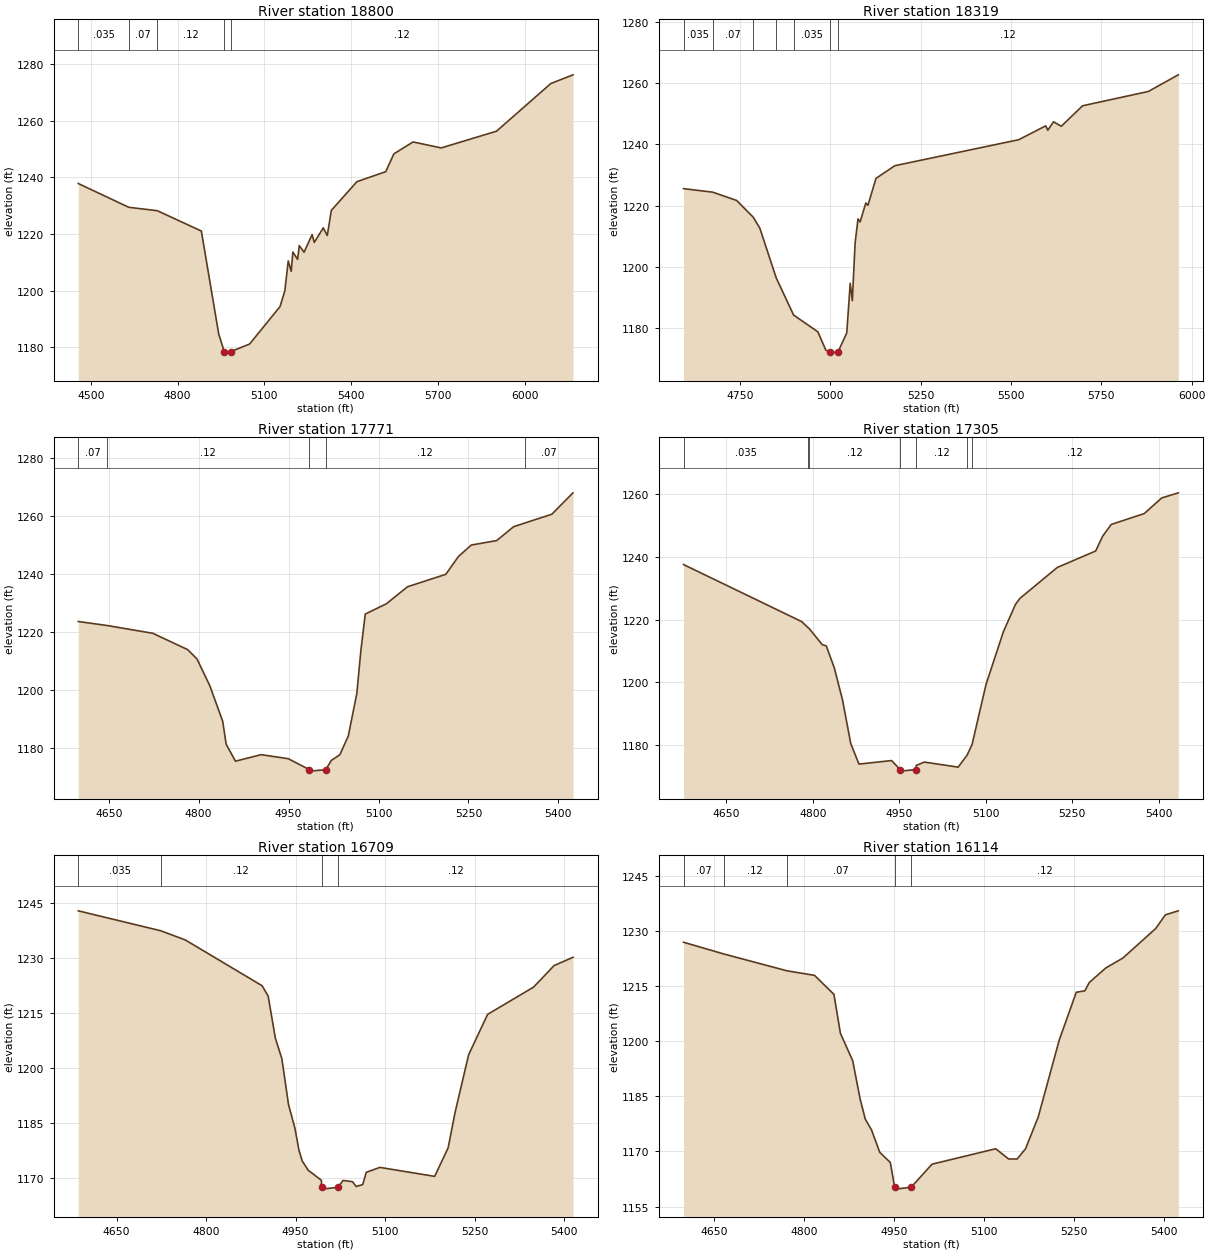
Type RM Length L Ch R = 1 ,18800   ,481,481,481
BEGIN DESCRIPTION:
SPRING CREEK_DS 32.0
END DESCRIPTION:
XS GIS Cut Line= 3
      2085360.94     13861019.79      2085330.56     13860477.44
      2084795.89     13859439.91
#Sta/Elev= 30
  4456.8 1237.87  4631.4 1229.45  4730.1 1228.24  4882.3 1221.05  4942.4 1184.59
  4961.6 1178.34  4962.1 1177.84  4983.3 1178.34  5049.1 1181.06  5154.3 1194.31
  5170.9 1199.87  5182.7 1210.48    5193 1206.79  5198.7 1213.61  5215.2 1211.02
  5220.8  1215.9  5237.4 1213.56  5265.2 1219.79  5272.7 1217.03  5303.9 1222.17
  5317.7 1219.46  5331.6 1228.35  5420.3 1238.53  5519.9 1242.06  5547.7 1248.34
  5614.2 1252.58  5711.5 1250.46  5902.7 1256.38  6090.5 1273.25  6167.2 1276.33
#Mann= 5 ,-1 , 0
  4456.8    .035       0  4631.4     .07       0  4730.1     .12       0
  4961.6     .05       0  4983.3     .12       0
Bank Sta=4961.6,4983.3
XS Rating Curve= 0 ,0
Exp/Cntr=0.3,0.1

Type RM Length L Ch R = 1 ,18319   ,548,548,548
BEGIN DESCRIPTION:
SPRING CREEK_DS 31.0
END DESCRIPTION:
XS GIS Cut Line= 3
        2085575.       13860825.      2085779.71     13860474.61
      2085296.99     13859641.33
#Sta/Elev= 30
  4594.2 1225.51  4674.9 1224.36  4740.9 1221.67  4786.9 1216.22  4805.4 1212.59
  4850.6 1196.41  4898.8 1184.27  4965.8 1178.82    4988 1172.81  5000.2 1172.36
  5000.7 1171.86    5022 1172.36  5045.8 1178.45  5055.4 1194.64  5061.2 1188.96
  5068.9 1207.77  5076.9 1215.65  5082.7 1214.65  5098.5 1220.82  5104.3 1220.05
  5126.7 1228.86  5178.8 1232.99  5521.7 1241.47  5596.3 1245.99  5602.1 1244.56
  5617.8 1247.32  5639.4 1245.86  5698.2 1252.53  5880.4 1257.21    5963 1262.63
#Mann= 7 ,-1 , 0
  4594.2    .035       0  4674.9     .07       0  4786.9    .035       0
  4850.6     .12       0  4898.8    .035       0  5000.2    .035       0
    5022     .12       0
Bank Sta=5000.2,5022
XS Rating Curve= 0 ,0
Exp/Cntr=0.3,0.1

Type RM Length L Ch R = 1 ,17771   ,466,466,466
BEGIN DESCRIPTION:
SPRING CREEK_DS 30.0
END DESCRIPTION:
XS GIS Cut Line= 3
      2085974.98     13861175.04      2086181.69     13860831.66
      2086475.03     13860524.96
#Sta/Elev= 30
  4599.2 1223.58  4647.3  1222.2  4723.5 1219.52  4781.8 1213.87  4797.3 1210.64
  4818.7  1201.4  4840.1 1189.16  4845.9 1181.25  4861.4 1175.41  4904.2 1177.66
  4949.4 1176.27  4984.8 1172.48  4985.3 1171.98    5012 1172.48  5021.3 1175.67
  5035.5 1177.64  5049.6  1184.1  5063.8 1198.74  5070.7 1213.85  5077.9 1226.15
  5113.1 1229.69  5148.4 1235.57  5212.2 1239.85  5233.3    1246  5254.7 1249.95
  5297.1 1251.49  5325.4 1256.28  5343.7 1257.53    5389 1260.57  5424.4 1267.96
#Mann= 5 ,-1 , 0
  4599.2     .07       0  4647.3     .12       0  4984.8     .05       0
    5012     .12       0  5343.7     .07       0
Bank Sta=4984.8,5012
XS Rating Curve= 0 ,0
Exp/Cntr=0.3,0.1

Type RM Length L Ch R = 1 ,17305   ,596,596,596
BEGIN DESCRIPTION:
SPRING CREEK_DS 29.0
END DESCRIPTION:
XS GIS Cut Line= 3
      2086125.03     13861524.97      2086411.42     13861211.77
      2086775.02     13860974.99
#Sta/Elev= 30
  4575.6 1237.52  4780.6 1219.35    4792 1217.37  4793.1 1217.26  4816.4 1211.99
  4823.2 1211.64  4837.3 1204.55  4851.5 1194.34  4865.7 1180.54  4879.9 1173.99
  4936.6 1175.11  4951.3 1172.25  4951.8 1171.75  4978.6 1172.25  4979.2 1173.56
  4993.4 1174.63    5052 1173.02  5067.3 1176.76  5076.1 1180.17  5100.3  1199.3
  5130.5 1216.12  5151.6 1224.87  5159.4 1226.78  5224.1  1236.6  5290.6 1241.83
  5302.6 1246.51  5317.6 1250.28    5375 1253.76  5405.2 1258.72  5433.9 1260.35
#Mann= 7 ,-1 , 0
  4575.6    .035       0    4792     .07       0  4793.1     .12       0
  4951.3     .05       0  4978.6     .12       0  5067.3     .07       0
  5076.1     .12       0
Bank Sta=4951.3,4978.6
XS Rating Curve= 0 ,0
Exp/Cntr=0.3,0.1

Type RM Length L Ch R = 1 ,16709   ,595,595,595
BEGIN DESCRIPTION:
SPRING CREEK_DS 28.0
END DESCRIPTION:
XS GIS Cut Line= 3
      2086325.01       13861875.      2086701.18     13861701.87
      2086874.99     13861325.02
#Sta/Elev= 30
  4585.9    1243  4724.1 1237.56  4765.3 1235.05  4894.1 1222.55  4904.2 1219.69
  4916.1 1208.31  4927.1 1202.65  4938.2 1190.17  4949.2 1183.53  4955.6 1177.76
  4961.2 1174.74  4971.2 1172.22  4993.2 1169.49  4993.9 1167.56  4994.4 1167.06
  5021.2 1167.56  5029.6 1169.43  5045.5 1169.09  5051.6 1167.77  5062.6 1168.31
  5068.5 1171.65  5091.4 1172.99  5183.2 1170.54  5205.8 1178.36  5217.2 1187.87
  5240.1 1203.74  5271.9 1214.75  5348.9 1222.18  5383.3 1228.06    5415 1230.32
#Mann= 4 ,-1 , 0
  4585.9    .035       0  4724.1     .12       0  4993.9     .05       0
  5021.2     .12       0
Bank Sta=4993.9,5021.2
XS Rating Curve= 0 ,0
Exp/Cntr=0.3,0.1

Type RM Length L Ch R = 1 ,16114   ,594,594,594
BEGIN DESCRIPTION:
SPRING CREEK_DS 27.0
END DESCRIPTION:
XS GIS Cut Line= 3
      2086774.95     13862175.01      2087158.49     13862057.96
      2087475.04     13861774.97
#Sta/Elev= 30
    4599 1226.95  4665.9 1223.77  4771.4 1219.18  4817.6 1217.93    4850 1212.76
  4860.8 1202.15  4881.3  1194.7  4893.6 1184.35  4902.3  1178.8  4912.7 1175.86
  4926.4 1169.78  4944.1 1166.98  4951.3 1160.24  4951.8 1159.74  4978.7 1160.24
  5013.7 1166.53  5119.9 1170.73  5141.6 1167.94  5155.8 1167.95  5169.7 1170.72
  5190.9 1179.38    5226 1200.33  5254.4 1213.33  5268.7 1213.72  5276.2    1216
  5303.8 1219.96  5332.2 1222.65    5387 1230.69  5403.2 1234.42  5424.6  1235.5
#Mann= 5 ,-1 , 0
    4599     .07       0  4665.9     .12       0  4771.4     .07       0
  4951.3     .05       0  4978.7     .12       0
Bank Sta=4951.3,4978.7
XS Rating Curve= 0 ,0
Exp/Cntr=0.3,0.1

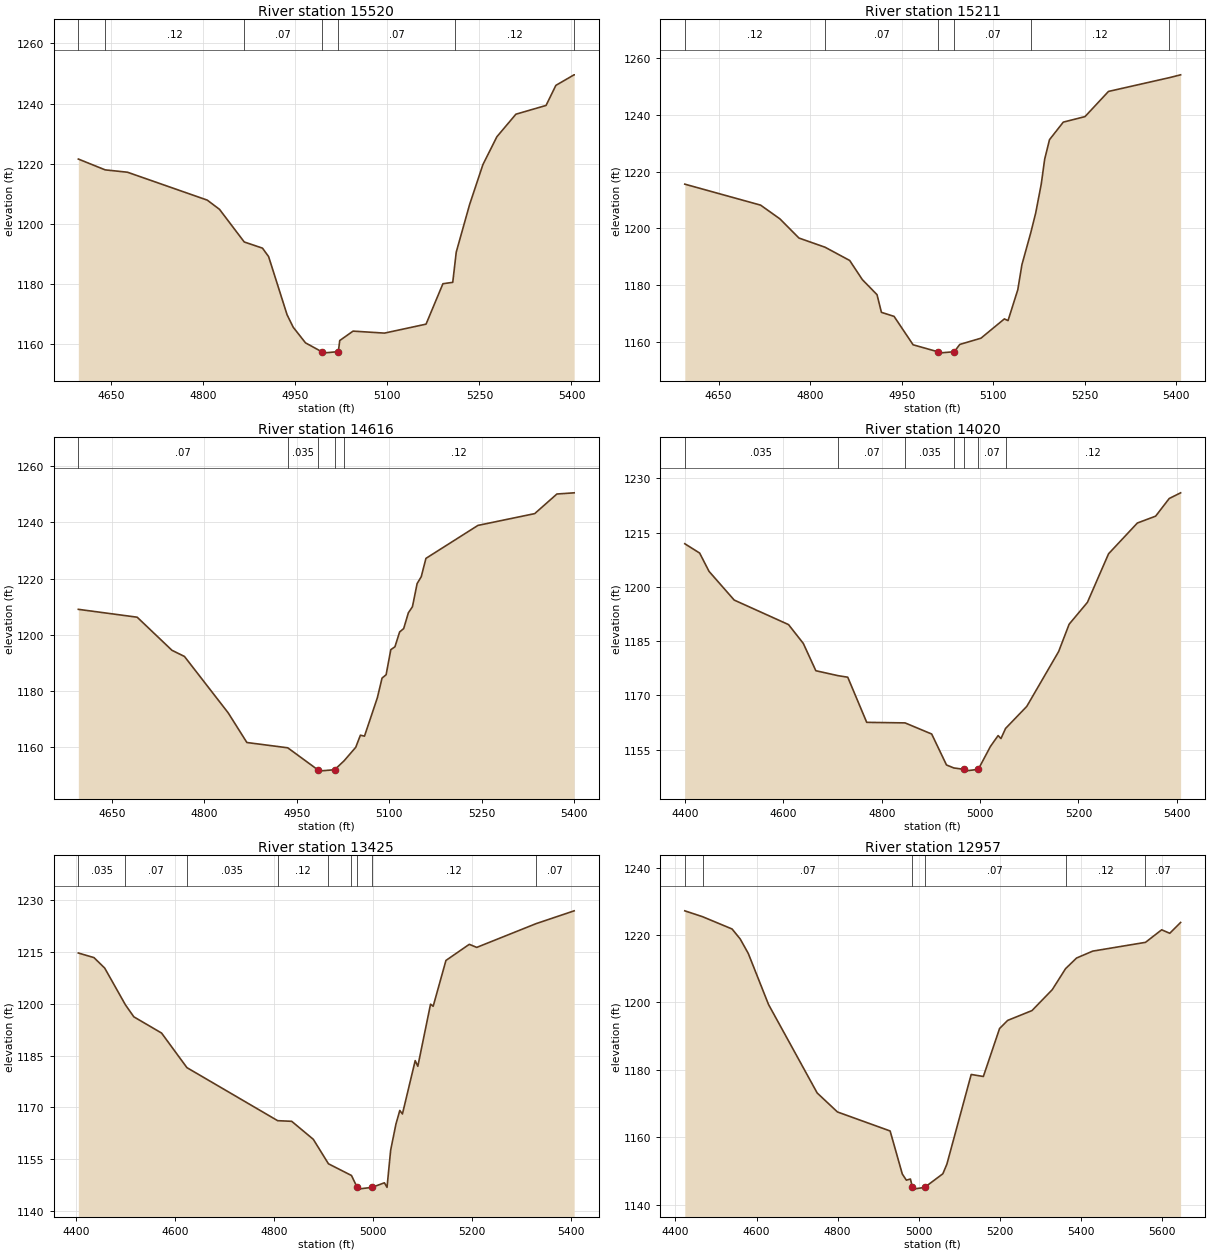
Type RM Length L Ch R = 1 ,15520   ,309,309,309
BEGIN DESCRIPTION:
SPRING CREEK_DS 26.0
END DESCRIPTION:
XS GIS Cut Line= 3
      2087174.96       13862475.      2087578.35     13862478.33
      2087775.02     13862124.97
#Sta/Elev= 30
  4596.6 1221.55  4640.3 1217.95  4676.6 1217.17  4806.6 1207.89  4826.6 1204.82
  4866.9 1193.96  4896.6 1191.91  4906.6  1189.1  4936.7 1169.74  4946.7 1165.59
  4966.7  1160.4  4992.8 1157.48  4993.3 1156.98  5020.2 1157.48  5022.5 1161.17
  5044.2  1164.3  5095.4 1163.64  5163.1 1166.62  5190.6 1180.07  5206.6 1180.53
  5210.2 1186.88  5212.3 1190.59    5234 1206.37  5255.7 1219.68  5278.5 1228.97
  5309.5 1236.47  5358.6 1239.38  5374.6 1246.06  5404.2 1249.57  5404.4 1249.57
#Mann= 7 ,-1 , 0
  4596.6     .07       0  4640.3     .12       0  4866.9     .07       0
  4992.8     .05       0  5020.2     .07       0  5210.2     .12       0
  5404.2     .07       0
Bank Sta=4992.8,5020.2
XS Rating Curve= 0 ,0
Exp/Cntr=0.3,0.1

Type RM Length L Ch R = 1 ,15211   ,595,595,595
BEGIN DESCRIPTION:
SPRING CREEK_DS 25.0
END DESCRIPTION:
XS GIS Cut Line= 3
      2087375.05     13862824.99      2087765.12     13862714.95
      2088124.97     13862525.01
#Sta/Elev= 30
  4594.7 1215.54  4718.9 1208.14  4750.5  1203.3  4781.7 1196.54  4824.6 1193.29
  4864.8 1188.63  4885.6 1181.86  4909.6 1176.57  4916.8 1170.34  4937.5 1168.92
  4968.7  1158.9  5008.8 1156.46  5009.3 1155.96  5036.2 1156.46  5045.1 1159.02
  5079.8 1161.22  5118.2 1168.03  5124.2 1167.43  5140.2 1178.33  5146.9 1187.12
  5161.4  1198.4  5169.5 1205.37  5178.6 1215.56  5184.2 1224.32  5192.1 1231.22
  5214.7 1237.41  5250.3 1239.36  5288.7 1248.23    5388 1253.07  5406.9 1254.09
#Mann= 6 ,-1 , 0
  4594.7     .12       0  4824.6     .07       0  5008.8     .05       0
  5036.2     .07       0  5161.4     .12       0    5388     .07       0
Bank Sta=5008.8,5036.2
XS Rating Curve= 0 ,0
Exp/Cntr=0.3,0.1

Type RM Length L Ch R = 1 ,14616   ,596,596,596
BEGIN DESCRIPTION:
SPRING CREEK_DS 24.0
END DESCRIPTION:
XS GIS Cut Line= 3
      2087574.98       13863175.      2087974.19     13863238.97
      2088274.99     13862975.01
#Sta/Elev= 30
  4595.7 1209.05  4691.2 1206.25  4747.6 1194.49  4767.9  1192.3  4838.8 1172.27
  4869.2 1161.71  4935.5 1159.83  4984.1 1152.04  4984.6 1151.54  5011.6 1152.04
    5027 1155.23  5045.8 1160.01  5053.4 1164.31    5060 1163.97  5080.9 1177.64
  5088.5 1184.61  5095.1  1185.8  5102.7 1194.71  5109.4 1195.73    5117    1201
  5123.6 1202.21  5131.2 1207.81  5137.8 1209.97  5145.4  1218.2  5152.1 1220.65
  5159.7 1227.16  5244.1 1238.88  5336.2 1243.07  5372.2 1250.04  5400.2 1250.46
#Mann= 5 ,-1 , 0
  4595.7     .07       0  4935.5    .035       0  4984.1    .035       0
  5011.6    .035       0    5027     .12       0
Bank Sta=4984.1,5011.6
XS Rating Curve= 0 ,0
Exp/Cntr=0.3,0.1

Type RM Length L Ch R = 1 ,14020   ,595,595,595
BEGIN DESCRIPTION:
SPRING CREEK_DS 23.0
END DESCRIPTION:
XS GIS Cut Line= 3
      2087424.95       13863875.      2088023.01     13863818.73
      2088375.02     13864025.01
#Sta/Elev= 30
  4399.3 1211.95  4429.5 1209.37  4448.6 1204.31  4499.8 1196.37  4610.3 1189.59
  4640.4 1184.38  4665.9 1176.83  4711.1 1175.46  4730.8 1175.04  4769.4 1162.55
  4847.4  1162.4  4901.6 1159.32  4931.7 1150.76  4946.6 1149.94  4966.8 1149.56
  4967.3 1149.06  4996.4 1149.56    5021 1155.87  5036.7 1158.89  5042.5 1158.07
  5051.9 1160.87    5095 1166.96  5159.8 1182.12  5181.2 1189.69  5218.4 1195.74
  5261.4 1209.17    5320 1217.68  5357.2 1219.58  5384.8 1224.46    5408 1226.03
#Mann= 7 ,-1 , 0
  4399.3    .035       0  4711.1     .07       0  4847.4    .035       0
  4946.6     .07       0  4966.8     .05       0  4996.4     .07       0
  5051.9     .12       0
Bank Sta=4966.8,4996.4
XS Rating Curve= 0 ,0
Exp/Cntr=0.3,0.1

Type RM Length L Ch R = 1 ,13425   ,468,468,468
BEGIN DESCRIPTION:
SPRING CREEK_DS 22.0
END DESCRIPTION:
XS GIS Cut Line= 3
      2087374.96     13864174.99      2087941.92     13864358.44
      2088325.04     13864224.98
#Sta/Elev= 30
  4404.1 1214.63  4435.7  1213.3  4457.4 1210.27  4499.2 1199.66  4516.2 1196.19
  4572.3 1191.49  4623.5  1181.5  4806.8 1166.17  4835.1 1165.99  4878.8 1160.78
  4909.4 1153.71  4955.9 1150.33  4967.4 1146.89  4967.9 1146.39  4997.1 1146.89
  5022.4 1148.22  5027.7  1146.9    5035 1157.62  5045.6 1165.14  5053.5 1169.13
  5058.8 1168.11  5084.6 1183.53  5089.9 1181.89  5115.6 1199.85  5120.9 1199.23
  5146.7 1212.48  5193.9 1217.14  5208.9 1216.25  5328.7 1223.11  5405.7 1226.82
#Mann= 9 ,-1 , 0
  4404.1    .035       0  4499.2     .07       0  4623.5    .035       0
  4806.8     .12       0  4909.4    .035       0  4955.9     .12       0
  4967.4     .05       0  4997.1     .12       0  5328.7     .07       0
Bank Sta=4967.4,4997.1
XS Rating Curve= 0 ,0
Exp/Cntr=0.3,0.1

Type RM Length L Ch R = 1 ,12957   ,724,724,724
BEGIN DESCRIPTION:
SPRING CREEK_DS 21.0
END DESCRIPTION:
XS GIS Cut Line= 2
       2087198.3      13864776.5      2088421.78     13864759.85
#Sta/Elev= 30
    4423 1227.15    4467  1225.4  4539.7 1221.76  4559.7 1218.81  4579.7  1214.5
  4629.7 1199.35  4749.7 1173.12  4799.7 1167.49  4929.7 1161.85  4959.8 1149.07
  4969.8 1147.26  4979.8  1147.6  4984.8  1145.1  4985.3  1144.6  5014.7  1145.1
  5059.8 1149.15  5069.8 1152.01  5129.8 1178.61  5159.8 1178.01  5199.8 1192.24
  5219.8 1194.65  5279.8 1197.56  5329.8 1203.76  5362.7    1210  5389.8 1213.15
  5429.8  1215.2  5559.9  1217.8  5599.8 1221.52  5619.8 1220.49  5646.6  1223.7
#Mann= 6 ,-1 , 0
    4423     .12       0    4467     .07       0  4984.8     .05       0
  5014.7     .07       0  5362.7     .12       0  5559.9     .07       0
Bank Sta=4984.8,5014.7
XS Rating Curve= 0 ,0
Exp/Cntr=0.3,0.1

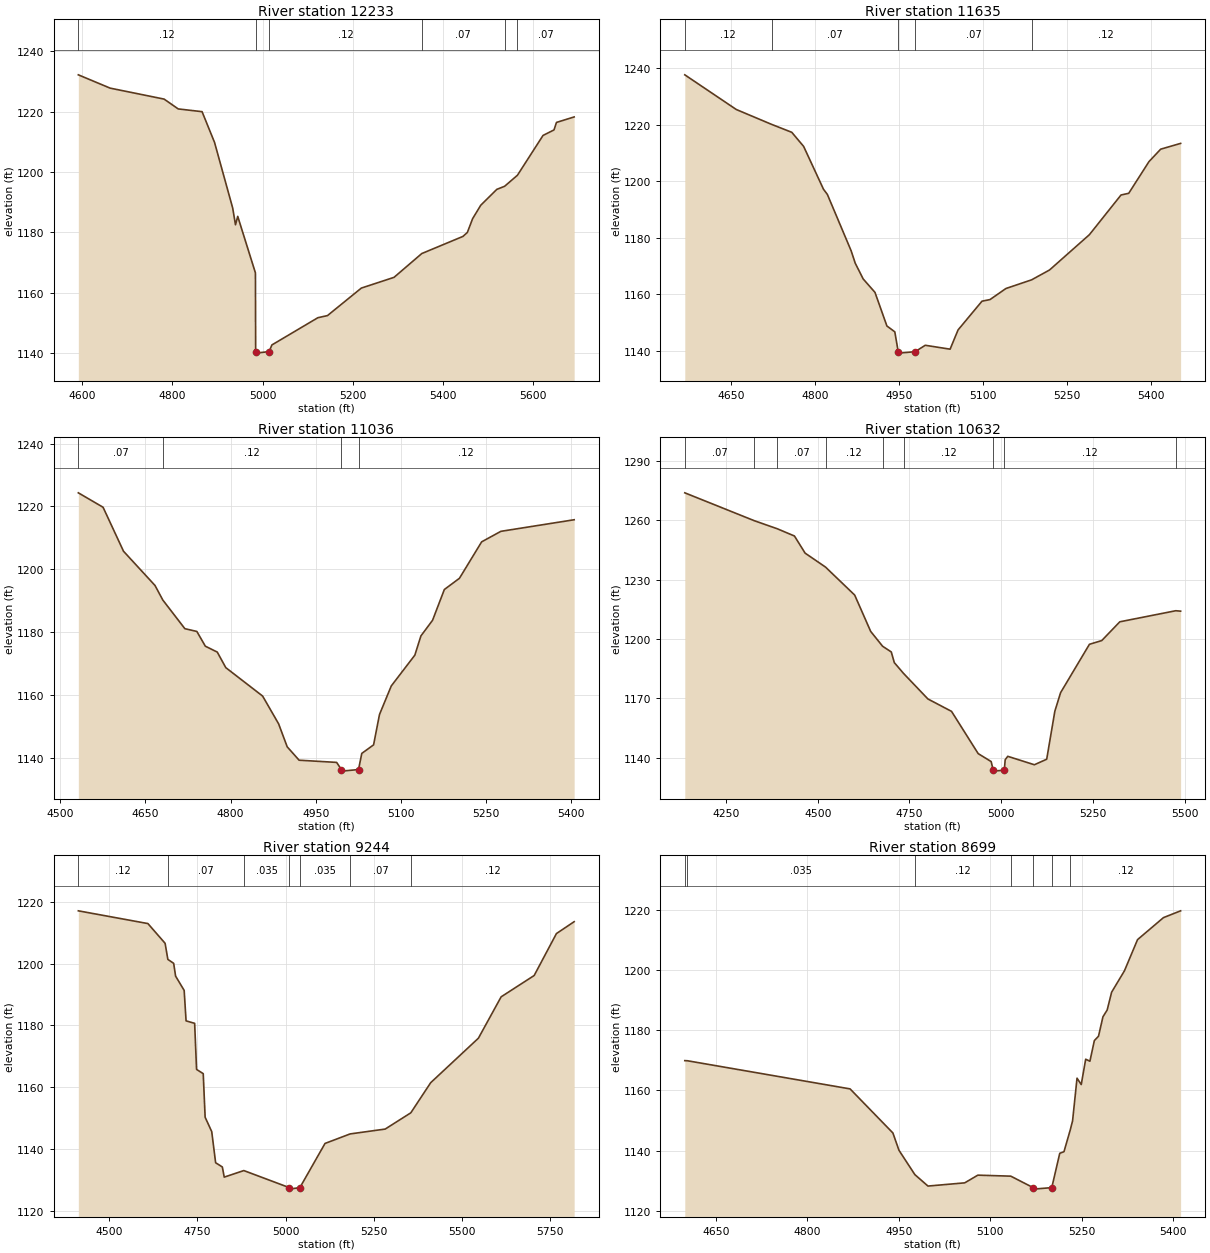
Type RM Length L Ch R = 1 ,12233   ,598,598,598
BEGIN DESCRIPTION:
SPRING CREEK_DS 20.0
END DESCRIPTION:
XS GIS Cut Line= 3
      2087375.01       13865375.      2087780.71     13865427.58
      2088424.97     13865175.01
#Sta/Elev= 30
  4590.9 1232.16  4661.5 1227.76  4781.4 1224.13  4812.7 1220.88  4865.7 1219.97
  4893.4  1209.8  4933.7 1188.09  4939.9 1182.55  4944.9 1185.33  4984.2 1166.63
  4984.7 1140.59  4985.2 1140.09  5014.6 1140.59  5020.7 1142.79  5122.8  1151.8
  5144.2 1152.51  5219.4 1161.61    5292 1165.16  5353.7 1173.04    5445  1178.7
  5454.8 1180.01  5466.5 1184.57  5484.6 1189.02  5520.2 1194.26  5537.6 1195.29
  5566.1 1198.95  5622.9 1212.11  5647.3 1213.94  5652.7 1216.41    5692 1218.23
#Mann= 6 ,-1 , 0
  4590.9     .12       0  4984.7     .05       0  5014.6     .12       0
  5353.7     .07       0  5537.6     .12       0  5566.1     .07       0
Bank Sta=4984.7,5014.6
XS Rating Curve= 0 ,0
Exp/Cntr=0.3,0.1

Type RM Length L Ch R = 1 ,11635   ,599,599,599
BEGIN DESCRIPTION:
SPRING CREEK_DS 19.0
END DESCRIPTION:
XS GIS Cut Line= 3
      2087925.02     13866074.98       2088226.7      13865765.2
      2088525.03     13865424.97
#Sta/Elev= 30
  4567.6 1237.66  4659.5 1225.38  4722.6 1220.11  4758.5 1217.31  4779.7 1212.31
  4815.1 1197.16  4822.1 1195.29  4864.5 1175.34  4871.7    1171  4885.9 1165.39
    4907 1160.63  4928.3 1148.72  4942.4 1146.65  4948.5 1139.61    4949 1139.11
  4978.7 1139.61  4996.7 1141.89  5041.1 1140.51  5055.3 1147.33    5098  1157.5
  5112.3 1158.07  5140.7 1161.99  5186.5 1165.06  5218.5 1168.54  5289.7 1181.05
  5346.1  1195.1  5359.9 1195.71    5396 1206.92  5416.9 1211.33  5452.5 1213.38
#Mann= 5 ,-1 , 0
  4567.6     .12       0  4722.6     .07       0  4948.5     .05       0
  4978.7     .07       0  5186.5     .12       0
Bank Sta=4948.5,4978.7
XS Rating Curve= 0 ,0
Exp/Cntr=0.3,0.1

Type RM Length L Ch R = 1 ,11036   ,404,404,404
BEGIN DESCRIPTION:
SPRING CREEK_DS 18.0
END DESCRIPTION:
XS GIS Cut Line= 3
        2088275.       13866375.      2088664.37       13866115.
        2088775.     13865724.99
#Sta/Elev= 30
  4531.8 1224.35  4575.4 1219.75  4611.4 1205.74  4666.9 1194.83  4680.7 1190.18
  4719.5 1181.06  4740.6 1180.18  4755.6 1175.48  4776.6  1173.6  4791.6 1168.65
  4856.5 1159.59  4884.7 1150.74  4899.8 1143.42  4920.8 1139.15  4986.9 1138.45
  4995.3 1136.17  4995.8 1135.67  5025.5 1136.17  5031.2 1141.31    5052 1144.04
  5062.4  1153.7  5083.2 1162.82  5124.7 1172.62  5135.4 1178.75  5155.9 1183.73
  5176.7 1193.54  5203.3 1197.12  5242.4 1208.73  5276.3 1212.08  5405.4 1215.77
#Mann= 4 ,-1 , 0
  4531.8     .07       0  4680.7     .12       0  4995.3     .05       0
  5025.5     .12       0
Bank Sta=4995.3,5025.5
XS Rating Curve= 0 ,0
Exp/Cntr=0.3,0.1

Type RM Length L Ch R = 1 ,10632   ,1388,1388,1388
BEGIN DESCRIPTION:
SPRING CREEK_DS 17.0
END DESCRIPTION:
XS GIS Cut Line= 3
      2088169.87      13866979.4      2088854.54     13866455.36
      2088990.36     13865985.82
#Sta/Elev= 30
  4137.8 1273.79  4327.7 1259.67  4389.7 1255.64  4436.6 1251.97  4465.6 1243.33
  4521.2 1236.28  4600.7 1222.14  4644.3 1203.78  4676.8 1196.28  4700.4  1193.4
  4708.7    1188  4733.8 1182.56  4800.2 1169.65  4864.6 1163.38  4937.2 1142.04
  4972.5 1138.03  4978.2 1133.69  4978.7 1133.19  5008.4 1133.69  5010.8 1138.96
  5017.8 1140.67  5090.3 1136.41  5123.9  1139.2  5146.1 1163.47  5161.7 1172.81
  5240.3 1197.26  5273.9 1199.15  5323.1 1208.63  5475.5 1214.22  5488.8 1214.01
#Mann= 9 ,-1 , 0
  4137.8     .07       0  4327.7    .035       0  4389.7     .07       0
  4521.2     .12       0  4676.8     .07       0  4733.8     .12       0
  4978.2     .05       0  5008.4     .12       0  5475.5     .07       0
Bank Sta=4978.2,5008.4
XS Rating Curve= 0 ,0
Exp/Cntr=0.3,0.1

Type RM Length L Ch R = 1 ,9244    ,545,545,545
BEGIN DESCRIPTION:
SPRING CREEK_DS 15.0
END DESCRIPTION:
XS GIS Cut Line= 3
      2089283.67     13867391.39      2089829.58     13867175.09
      2090324.97     13866525.04
#Sta/Elev= 30
  4412.8 1217.13  4609.9    1213  4658.6 1206.61  4666.4  1201.4  4682.9 1200.11
  4688.3 1195.99  4712.6 1191.35    4718 1181.48  4742.3 1180.68  4747.7 1165.75
  4766.6 1164.38    4772 1150.26  4790.7 1145.59  4801.7 1135.52  4820.7 1134.15
  4826.1 1130.86  4881.6 1132.98  5010.1 1127.47  5010.6 1126.97  5040.4 1127.47
  5111.6 1141.77  5182.6 1144.85  5282.1 1146.43  5354.6 1151.69  5410.9 1161.45
  5546.1 1175.87  5610.5 1189.27    5704 1196.17  5767.1 1209.76  5817.3 1213.61
#Mann= 7 ,-1 , 0
  4412.8     .12       0  4666.4     .07       0  4881.6    .035       0
  5010.1    .035       0  5040.4    .035       0  5182.6     .07       0
  5354.6     .12       0
Bank Sta=5010.1,5040.4
XS Rating Curve= 0 ,0
Exp/Cntr=0.3,0.1

Type RM Length L Ch R = 1 ,8699    ,592,592,592
BEGIN DESCRIPTION:
SPRING CREEK_DS 14.0
END DESCRIPTION:
XS GIS Cut Line= 3
        2090375.     13867475.04      2090343.34     13867075.39
      2090625.01     13866774.99
#Sta/Elev= 30
  4599.1 1169.94  4603.4  1169.9    4870 1160.53  4940.2 1145.85  4950.2 1140.07
  4976.2 1131.98  4997.7 1128.17  5057.9 1129.24  5079.4  1131.8  5133.4 1131.47
  5170.1 1127.65  5170.6 1127.15  5200.6 1127.65  5213.7 1139.08  5220.6 1139.61
  5230.7 1146.72  5234.7 1149.88    5242  1164.1  5248.9 1161.97  5256.2 1170.42
  5263.1 1169.74  5270.4 1176.62  5277.2 1178.07  5284.5 1184.55  5291.4 1186.79
  5298.7 1192.73  5319.7 1199.85  5341.2 1210.24  5383.7 1217.57  5411.8 1219.83
#Mann= 7 ,-1 , 0
  4599.1     .07       0  4603.4    .035       0  4976.2     .12       0
  5133.4     .07       0  5170.1     .05       0  5200.6     .07       0
  5230.7     .12       0
Bank Sta=5170.1,5200.6
XS Rating Curve= 0 ,0
Exp/Cntr=0.3,0.1

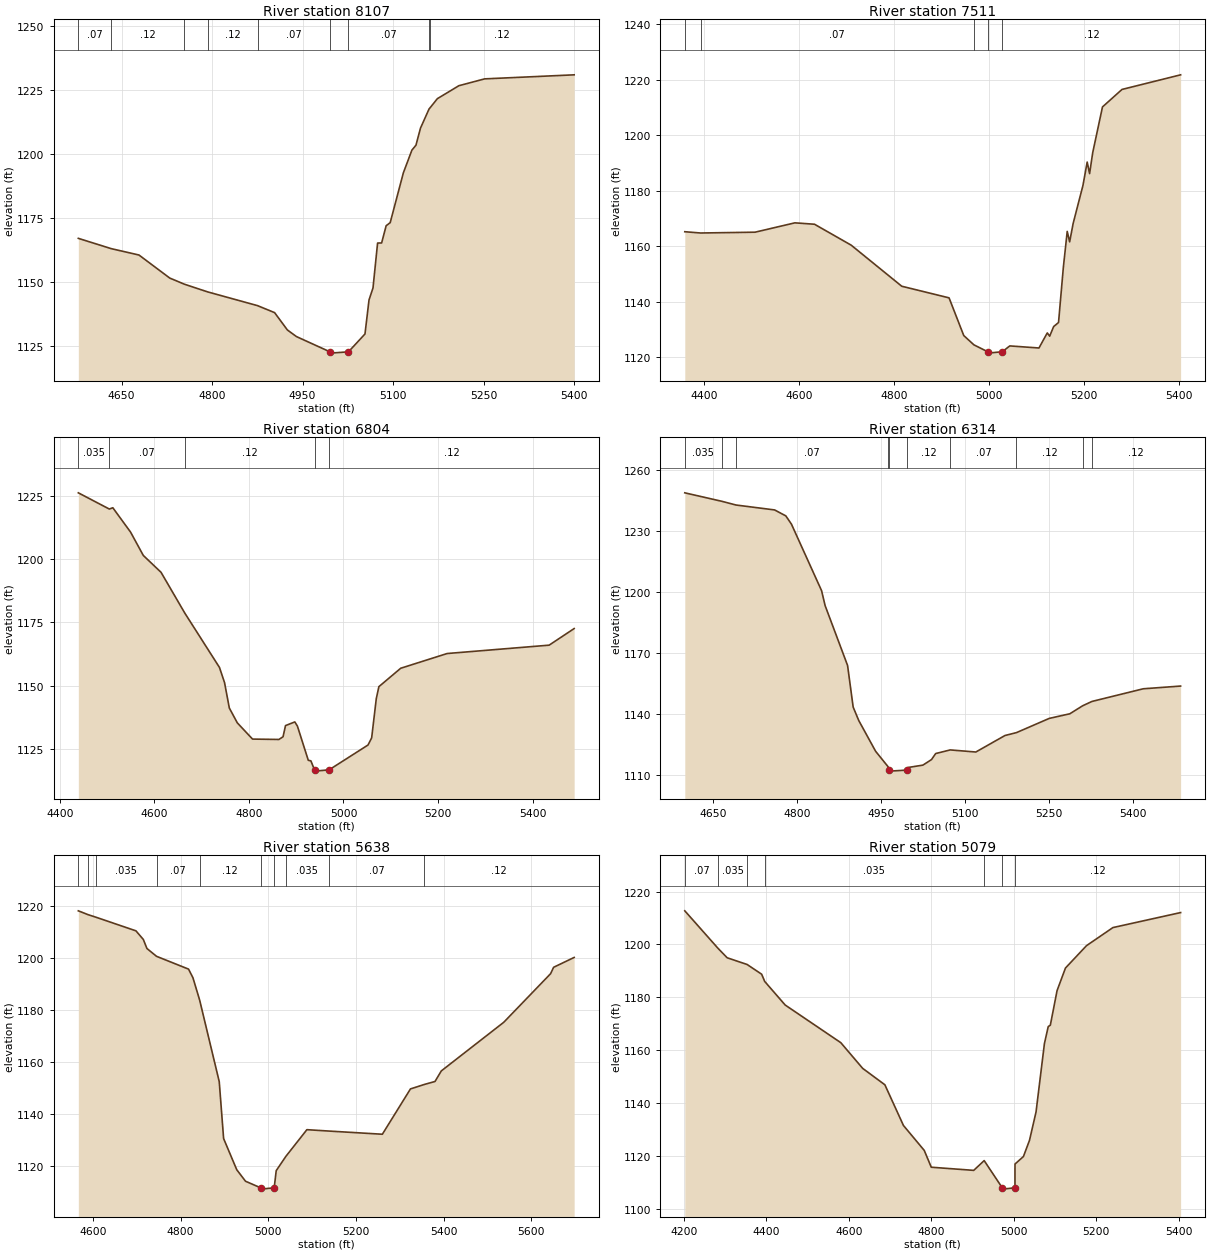
Type RM Length L Ch R = 1 ,8107    ,596,596,596
BEGIN DESCRIPTION:
SPRING CREEK_DS 13.0
END DESCRIPTION:
XS GIS Cut Line= 3
        2090475.       13867425.      2090824.99     13867189.76
      2091124.97     13866925.02
#Sta/Elev= 30
  4578.3 1167.16  4632.9 1163.14  4678.8 1160.66  4729.8 1151.67  4754.1 1149.27
  4792.8 1146.26  4875.3 1140.91  4903.6 1138.18  4924.8 1131.42  4939.8 1128.84
  4995.4 1122.88  4995.9 1122.38    5026 1122.88  5053.4 1129.85  5060.1 1143.13
  5066.7 1147.81  5074.3 1165.33    5081 1165.36  5088.5 1172.09  5095.2 1173.29
    5117 1192.71  5131.2 1201.59  5137.9  1203.5  5145.4 1210.16  5159.7 1217.68
  5160.5 1217.87  5173.4 1221.66    5209 1226.71  5251.7 1229.38  5400.1 1230.96
#Mann= 9 ,-1 , 0
  4578.3     .07       0  4632.9     .12       0  4754.1     .07       0
  4792.8     .12       0  4875.3     .07       0  4995.4     .05       0
    5026     .07       0  5159.7     .07       0  5160.5     .12       0
Bank Sta=4995.4,5026
XS Rating Curve= 0 ,0
Exp/Cntr=0.3,0.1

Type RM Length L Ch R = 1 ,7511    ,707,707,707
BEGIN DESCRIPTION:
SPRING CREEK_DS 12.0
END DESCRIPTION:
XS GIS Cut Line= 3
      2090140.76     13867474.65      2090733.16     13867718.95
      2091124.95     13867625.01
#Sta/Elev= 30
  4359.2 1165.21  4392.3 1164.75  4507.1 1165.04  4590.9 1168.41  4632.2 1167.91
  4709.4 1160.37  4815.9 1145.55  4915.5 1141.36  4946.4 1127.77  4967.8 1124.41
  4996.9 1121.93  4997.4 1121.43  5027.5 1121.93  5043.3 1124.03  5104.7 1123.28
  5122.2 1128.72  5127.3 1127.55  5135.6    1131  5145.9 1132.47  5156.1 1152.46
  5164.2 1165.32  5169.3 1161.57  5176.7 1168.22  5197.3  1181.9  5206.2 1190.32
  5211.3 1186.17  5217.8 1193.68  5238.4 1210.21  5279.5 1216.52  5402.9 1221.79
#Mann= 5 ,-1 , 0
  4359.2    .035       0  4392.3     .07       0  4967.8     .12       0
  4996.9     .05       0  5027.5     .12       0
Bank Sta=4996.9,5027.5
XS Rating Curve= 0 ,0
Exp/Cntr=0.3,0.1

Type RM Length L Ch R = 1 ,6804    ,490,490,490
BEGIN DESCRIPTION:
SPRING CREEK 11.0
END DESCRIPTION:
XS GIS Cut Line= 4
      2089790.43     13868047.93      2090223.84     13868185.46
      2090453.05     13868289.64      2090786.49     13868210.45
#Sta/Elev= 30
  4438.9 1226.11  4504.5 1219.71  4511.9 1220.22  4549.4 1210.63  4576.4 1201.41
  4613.9 1194.76  4664.3 1178.64  4737.5 1157.25  4748.3 1151.24  4758.4 1141.23
  4775.3 1135.38  4807.5 1128.97  4863.3 1128.82  4872.1 1129.88  4877.3 1134.29
    4897 1135.74  4902.5 1134.09  4925.5 1120.61    4931 1120.38  4938.7 1116.83
  4939.2 1116.33  4969.5 1116.83  5051.9 1126.63  5059.6 1129.45  5069.4 1144.92
  5074.9 1149.65  5121.1 1156.91  5219.3 1162.72  5435.2 1166.02  5488.1 1172.57
#Mann= 5 ,-1 , 0
  4438.9    .035       0  4504.5     .07       0  4664.3     .12       0
  4938.7     .05       0  4969.5     .12       0
Bank Sta=4938.7,4969.5
XS Rating Curve= 0 ,0
Exp/Cntr=0.3,0.1

Type RM Length L Ch R = 1 ,6314    ,676,676,676
BEGIN DESCRIPTION:
SPRING CREEK_DS 10.0
END DESCRIPTION:
XS GIS Cut Line= 3
      2089724.95       13868675.      2090124.69     13868650.26
      2090536.57     13868394.76
#Sta/Elev= 30
  4599.5 1248.61  4665.7 1244.44  4690.9 1242.62  4759.9  1240.2  4779.9 1237.27
  4789.9 1233.23  4843.7 1200.53    4850 1193.21  4890.1 1163.79  4900.1 1143.32
  4910.1 1136.71  4940.2 1121.61  4962.5    1114  4964.9 1112.36  4965.4 1111.86
  4995.7 1112.36  4997.7 1113.63  5024.6 1114.81    5040 1117.54  5047.4  1120.5
  5073.4 1122.28  5119.1 1121.25  5171.1 1129.36  5191.6 1130.78  5250.2 1137.77
  5286.9 1140.04  5309.9 1143.99  5326.4  1146.1    5418 1152.32  5484.7 1153.66
#Mann= 10 ,-1 , 0
  4599.5    .035       0  4665.7     .12       0  4690.9     .07       0
  4962.5     .12       0  4964.9     .05       0  4995.7     .12       0
  5073.4     .07       0  5191.6     .12       0  5309.9    .035       0
  5326.4     .12       0
Bank Sta=4964.9,4995.7
XS Rating Curve= 0 ,0
Exp/Cntr=0.3,0.1

Type RM Length L Ch R = 1 ,5638    ,559,559,559
BEGIN DESCRIPTION:
SPRING CREEK_DS 9.0
END DESCRIPTION:
XS GIS Cut Line= 3
      2090657.26     13869156.46      2090669.76     13868473.01
      2090948.95     13868122.98
#Sta/Elev= 30
  4566.6  1218.1  4589.1 1216.61  4605.9  1215.7  4698.1 1210.41  4714.9  1207.1
  4723.1 1203.64    4745 1200.63  4818.1 1195.71  4828.1  1192.4  4843.4 1183.83
  4888.1 1152.51  4898.1 1130.63  4928.1 1118.66  4948.1 1114.25  4982.7 1111.72
  4983.2 1111.22  5013.5 1111.72  5018.1 1118.31  5040.1 1123.79  5088.1 1134.05
  5138.4 1133.52  5260.3  1132.3  5324.4  1149.7  5356.3 1151.43  5380.4 1152.56
  5394.8 1156.62  5537.3  1175.3  5644.2 1193.97    5651 1196.41  5697.9  1200.2
#Mann= 10 ,-1 , 0
  4566.6    .035       0  4589.1     .07       0  4605.9    .035       0
    4745     .07       0  4843.4     .12       0  4982.7     .05       0
  5013.5     .12       0  5040.1    .035       0  5138.4     .07       0
  5356.3     .12       0
Bank Sta=4982.7,5013.5
XS Rating Curve= 0 ,0
Exp/Cntr=0.3,0.1

Type RM Length L Ch R = 1 ,5079    ,512,512,512
BEGIN DESCRIPTION:
SPRING CREEK_DS 8.0
END DESCRIPTION:
XS GIS Cut Line= 3
      2090794.77     13869252.34      2091103.17     13868623.04
      2091203.18     13868131.32
#Sta/Elev= 30
  4202.3 1212.74  4282.8 1198.56  4305.1 1194.97  4353.5 1192.43  4388.7 1188.75
  4396.1 1186.02  4445.7  1177.1  4580.7 1162.84  4633.7 1153.12  4687.6  1146.9
  4732.6 1131.51  4783.1 1122.06  4800.1  1115.7  4903.1 1114.51  4928.4 1118.21
  4972.3 1107.91  4972.8 1107.41  5003.1 1107.91  5003.2 1116.91  5023.6 1119.74
  5038.3 1125.84  5054.2 1136.59  5074.6 1162.53  5083.8 1168.93  5088.9 1169.47
  5105.2 1182.53  5125.6 1191.09  5176.6 1199.55  5240.7  1206.4  5404.9 1212.08
#Mann= 7 ,-1 , 0
  4202.3     .07       0  4282.8    .035       0  4353.5     .07       0
  4396.1    .035       0  4928.4     .12       0  4972.3     .05       0
  5003.1     .12       0
Bank Sta=4972.3,5003.1
XS Rating Curve= 0 ,0
Exp/Cntr=0.3,0.1