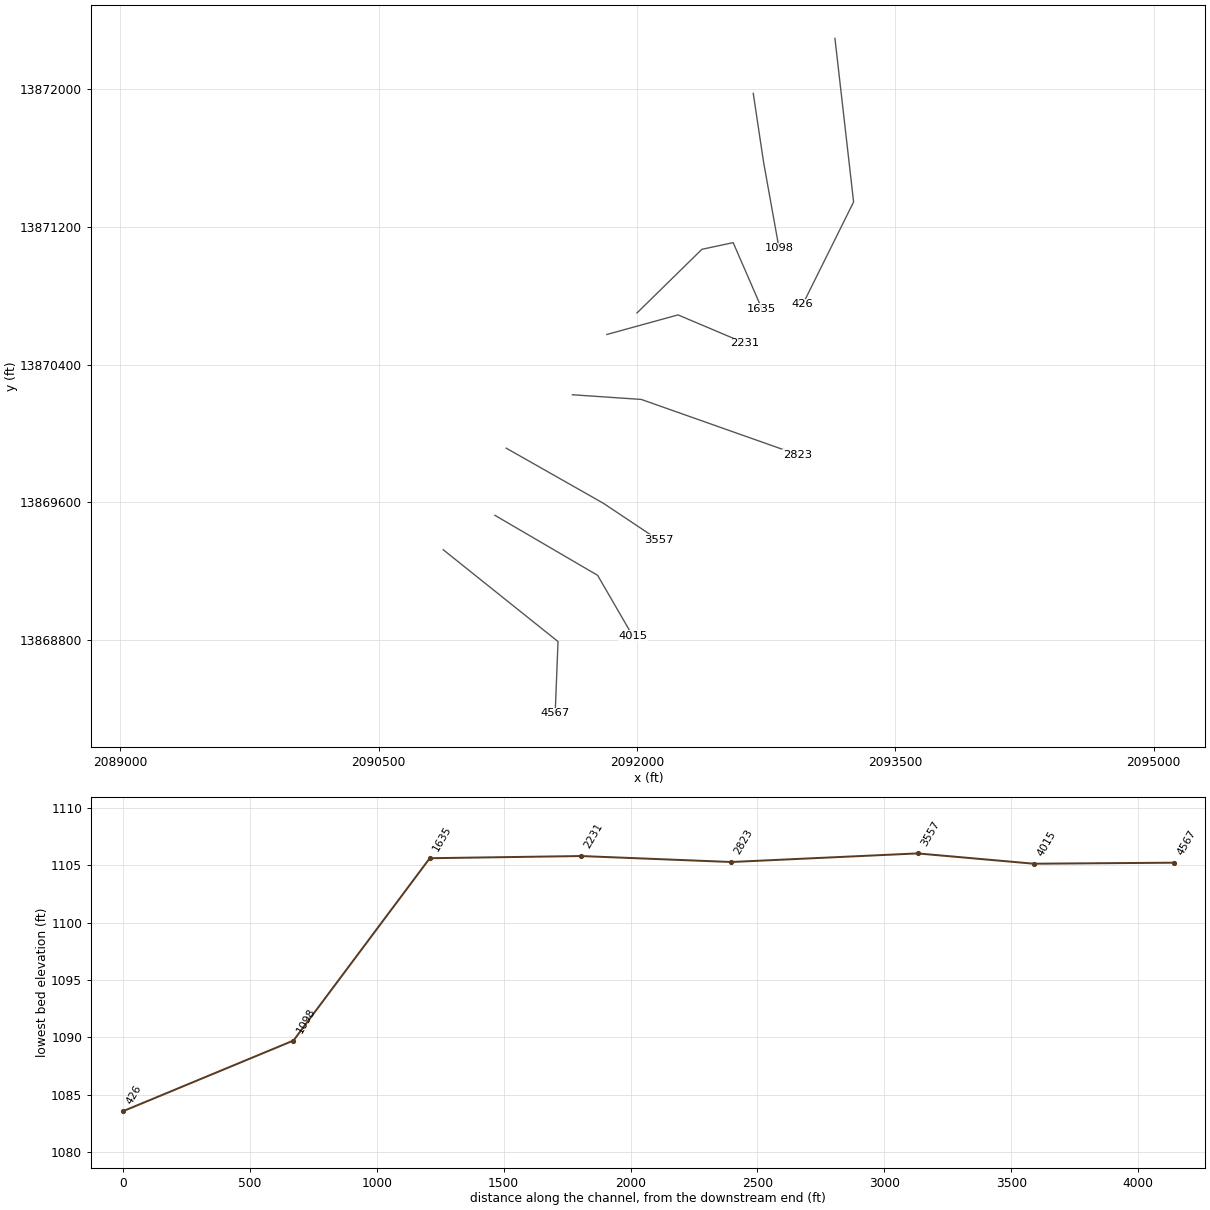
HEC-RAS study SPRING CREEK.prj: SPRING CREEK Base Level Engineering

--- SPRING CREEK.g01 (geometry) --- (continued)

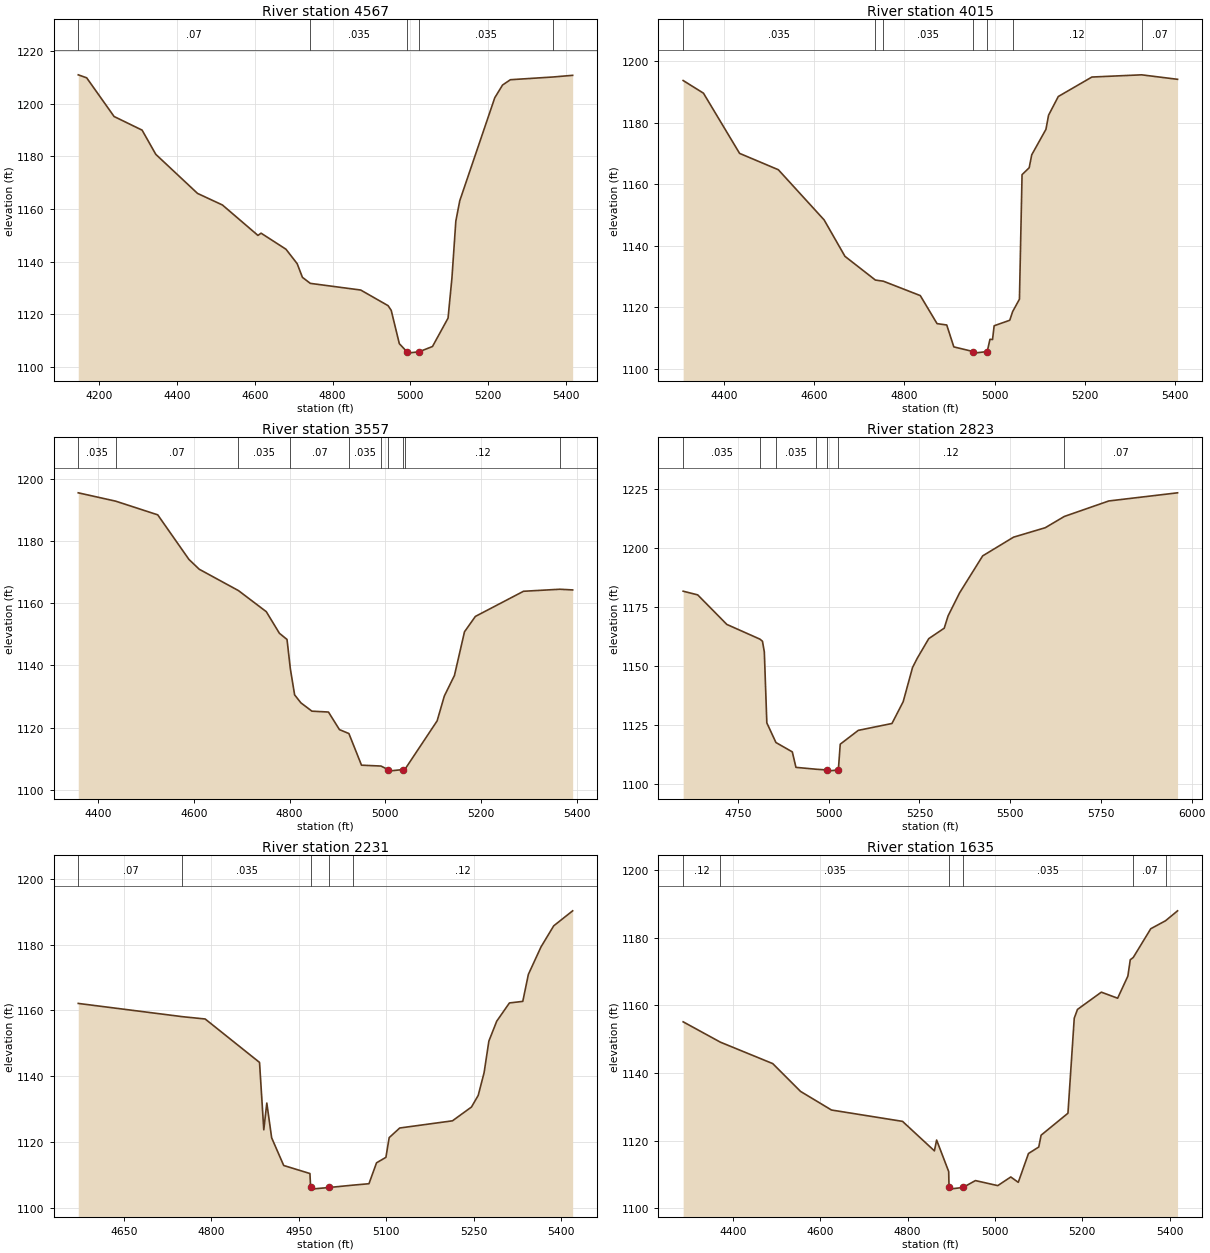
Type RM Length L Ch R = 1 ,4567    ,552,552,552
BEGIN DESCRIPTION:
SPRING CREEK_DS 7.0
END DESCRIPTION:
XS GIS Cut Line= 3
      2090874.99     13869325.01      2091541.56     13868791.95
        2091525.     13868374.98
#Sta/Elev= 30
  4146.5    1211  4168.1 1209.87  4238.6 1195.16  4310.6 1189.98  4345.8 1180.78
  4453.1 1165.93  4517.1 1161.53  4608.4 1149.97  4616.4 1150.82  4680.4 1144.72
  4709.2 1139.23  4722.7 1134.03    4743 1131.74  4872.5 1129.21  4942.9 1123.27
  4950.9  1121.5  4971.8 1108.82  4991.5 1105.73    4992 1105.23  5022.4 1105.73
    5057 1107.75    5097 1118.53    5107 1133.79    5117 1155.38  5127.1 1163.14
  5217.1 1202.29  5237.1 1207.12  5257.2 1209.14  5367.1 1210.18  5417.3 1210.81
#Mann= 5 ,-1 , 0
  4146.5     .07       0    4743    .035       0  4991.5    .035       0
  5022.4    .035       0  5367.1     .07       0
Bank Sta=4991.5,5022.4
XS Rating Curve= 0 ,0
Exp/Cntr=0.3,0.1

Type RM Length L Ch R = 1 ,4015    ,458,458,458
BEGIN DESCRIPTION:
SPRING CREEK_DS 6.0
END DESCRIPTION:
XS GIS Cut Line= 3
      2091175.03     13869524.99      2091771.46     13869176.46
      2091974.98     13868825.04
#Sta/Elev= 30
  4309.2 1193.78  4354.2 1189.67  4434.4 1170.09  4520.4 1164.77    4622 1148.45
  4668.2 1136.61  4735.7  1128.9  4753.5 1128.52  4835.3 1123.85  4872.5 1114.73
    4894 1114.29  4909.7 1107.17  4952.9 1105.64  4953.4 1105.14  4983.8 1105.64
  4989.9 1109.63  4995.6 1109.57  4999.2 1114.04  5033.8 1115.83  5040.2 1118.64
  5055.3 1122.68  5061.1 1163.17  5076.9 1165.41  5082.6 1169.63  5114.1 1177.91
  5119.9 1182.49  5141.5 1188.58    5216 1194.91  5326.3 1195.63  5406.1 1194.17
#Mann= 7 ,-1 , 0
  4309.2    .035       0  4735.7     .07       0  4753.5    .035       0
  4952.9    .035       0  4983.8    .035       0  5040.2     .12       0
  5326.3     .07       0
Bank Sta=4952.9,4983.8
XS Rating Curve= 0 ,0
Exp/Cntr=0.3,0.1

Type RM Length L Ch R = 1 ,3557    ,734,734,734
BEGIN DESCRIPTION:
SPRING CREEK_DS 5.0
END DESCRIPTION:
XS GIS Cut Line= 3
      2091240.73     13869914.92      2091804.73     13869594.96
      2092123.96     13869382.14
#Sta/Elev= 30
    4359 1195.43  4437.2 1192.75  4524.9 1188.36    4590 1174.05  4611.6 1170.88
  4693.4 1164.03  4751.5 1157.26  4778.9 1150.32  4794.8 1148.33  4801.8 1138.85
  4810.7 1130.53  4823.8 1127.97  4846.8  1125.3  4881.3 1125.02  4904.3 1119.37
    4924 1118.11  4950.3 1107.95    4991 1107.67  5005.6 1106.54  5006.1 1106.04
  5036.5 1106.54  5040.9 1106.61  5108.2 1122.19  5123.2 1130.16  5144.3 1136.76
  5165.3  1150.8    5188 1155.73  5288.5 1163.81  5364.4 1164.46  5391.1 1164.24
#Mann= 10 ,-1 , 0
    4359    .035       0  4437.2     .07       0  4693.4    .035       0
  4801.8     .07       0    4924    .035       0    4991     .07       0
  5005.6     .05       0  5036.5     .07       0  5040.9     .12       0
  5364.4     .07       0
Bank Sta=5005.6,5036.5
XS Rating Curve= 0 ,0
Exp/Cntr=0.3,0.1

Type RM Length L Ch R = 1 ,2823    ,592,592,592
BEGIN DESCRIPTION:
SPRING CREEK_DS 4.0
END DESCRIPTION:
XS GIS Cut Line= 3
      2091625.02       13870225.       2092024.8     13870197.88
      2092931.16     13869877.85
#Sta/Elev= 30
  4599.3 1181.61  4639.4 1180.05  4719.6 1167.52    4811 1161.26  4817.8 1160.37
  4822.9 1155.83  4829.8 1125.76  4854.9 1117.42    4900 1113.45    4910 1106.89
  4965.8 1106.09  4994.8 1105.79  4995.3 1105.29  5026.8 1105.79    5032 1116.72
  5081.7 1122.58  5174.5  1125.5  5205.4 1134.74  5231.1 1149.22  5244.1 1153.16
  5275.9  1161.5  5318.4 1165.92  5329.1 1171.15  5360.8 1180.91  5424.4  1196.6
  5509.4 1204.53  5596.9 1208.55  5649.3 1213.32  5771.8 1219.89  5961.2 1223.34
#Mann= 7 ,-1 , 0
  4599.3    .035       0    4811     .07       0  4854.9    .035       0
  4965.8     .12       0  4994.8     .05       0  5026.8     .12       0
  5649.3     .07       0
Bank Sta=4994.8,5026.8
XS Rating Curve= 0 ,0
Exp/Cntr=0.3,0.1

Type RM Length L Ch R = 1 ,2231    ,596,596,596
BEGIN DESCRIPTION:
SPRING CREEK_DS 3.0
END DESCRIPTION:
XS GIS Cut Line= 3
        2091825.       13870575.      2092238.26     13870688.65
      2092624.96     13870525.02
#Sta/Elev= 30
  4571.4 1162.14  4750.2 1158.12  4789.2 1157.42  4882.5 1144.25  4889.8  1123.8
    4895 1131.92  4903.3 1121.38    4924 1112.98    4969 1110.54  4970.2 1106.31
  4970.7 1105.81  5002.2 1106.31  5042.3 1107.01  5070.3 1107.45  5083.3 1113.79
  5099.4 1115.45    5105 1121.43  5123.1 1124.35  5213.6 1126.53  5246.2 1130.71
  5257.8 1134.23  5267.9 1141.13  5276.1 1150.71  5289.6 1156.76  5311.4 1162.29
  5334.3 1162.76  5343.9 1170.95  5365.6 1179.29  5387.4 1185.68  5419.9 1190.23
#Mann= 5 ,-1 , 0
  4571.4     .07       0  4750.2    .035       0  4970.2    .035       0
  5002.2    .035       0  5042.3     .12       0
Bank Sta=4970.2,5002.2
XS Rating Curve= 0 ,0
Exp/Cntr=0.3,0.1

Type RM Length L Ch R = 1 ,1635    ,537,537,537
BEGIN DESCRIPTION:
SPRING CREEK_DS 2.0
END DESCRIPTION:
XS GIS Cut Line= 4
      2092000.03     13870700.03      2092376.98     13871069.54
      2092558.43     13871108.29      2092724.99     13870725.02
#Sta/Elev= 30
  4286.6 1155.15  4371.9 1149.12  4491.6 1142.78  4555.3 1134.54    4626 1129.04
  4788.6 1125.68  4861.5 1116.95  4866.6 1120.15  4894.2 1110.83    4895 1106.12
  4895.5 1105.62    4927 1106.12  4955.4 1108.15  5006.5 1106.66  5036.3 1109.22
  5053.4 1107.63  5076.8 1116.17  5100.3 1118.09  5105.7 1121.59  5167.1 1128.09
  5181.5 1156.22  5188.9 1158.82  5243.5 1163.93  5280.8 1162.14  5304.2 1168.68
  5309.7 1173.52  5316.6 1174.22  5356.6 1182.71  5390.4 1185.07  5417.9 1188.01
#Mann= 6 ,-1 , 0
  4286.6     .12       0  4371.9    .035       0    4895     .05       0
    4927    .035       0  5316.6     .07       0  5390.4     .12       0
Bank Sta=4895,4927
XS Rating Curve= 0 ,0
Exp/Cntr=0.3,0.1

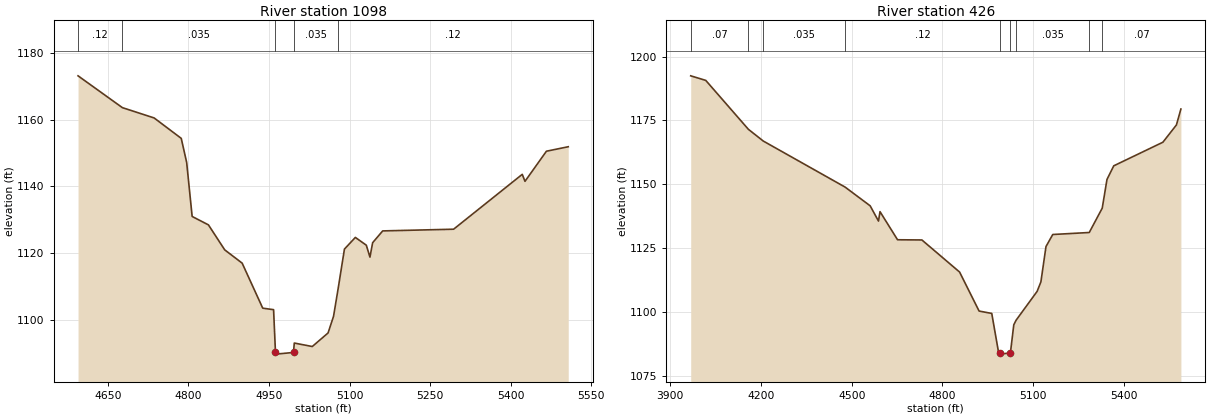
Type RM Length L Ch R = 1 ,1098    ,672,672,672
BEGIN DESCRIPTION:
SPRING CREEK_DS 1.0
END DESCRIPTION:
XS GIS Cut Line= 3
        2092675.     13871974.99      2092735.33      13871573.9
        2092825.       13871075.
#Sta/Elev= 30
  4594.4  1173.1  4676.9 1163.57    4736 1160.48  4786.5 1154.36  4796.6 1147.14
  4806.8 1130.96  4837.1 1128.44  4867.4 1120.96  4899.9 1116.97  4938.2 1103.48
  4958.4 1103.03  4961.9 1090.21  4962.5 1089.71  4995.5 1090.21  4996.9 1093.03
  5030.4 1091.99  5059.8 1096.05    5070 1101.04  5078.7 1109.47  5090.3 1121.19
  5110.6 1124.68    5131 1122.35  5137.8 1118.78  5142.8  1123.1  5161.5 1126.63
  5293.5 1127.14  5421.3 1143.58  5426.4 1141.49  5466.3 1150.51  5506.9 1151.85
#Mann= 5 ,-1 , 0
  4594.4     .12       0  4676.9    .035       0  4961.9    .035       0
  4995.5    .035       0  5078.7     .12       0
Bank Sta=4961.9,4995.5
XS Rating Curve= 0 ,0
Exp/Cntr=0.3,0.1

Type RM Length L Ch R = 1 ,426     ,0,0,0
BEGIN DESCRIPTION:
SPRING CREEK_DS 0.0
END DESCRIPTION:
XS GIS Cut Line= 3
      2093149.38     13872294.52      2093257.74     13871344.37
      2092962.23      13870749.2
#Sta/Elev= 30
  3967.5 1192.46  4017.3 1190.67  4158.2 1171.53  4207.5 1166.93  4477.9 1148.92
  4560.8 1141.59  4588.4 1135.62  4593.4  1139.3  4651.4  1128.3  4731.9 1128.22
  4856.6 1115.66    4921  1100.4  4962.9 1099.46  4985.3  1084.3  4990.9 1084.04
  4991.6 1083.54  5024.6 1084.04  5035.7    1095  5043.3  1096.8  5112.9  1108.1
  5125.4 1111.82  5142.2 1125.64  5164.6 1130.36  5285.3 1131.14  5328.2 1140.68
  5343.9 1151.91  5366.3 1157.24  5528.7 1166.47  5573.5 1173.24  5588.3 1179.46
#Mann= 9 ,-1 , 0
  3967.5     .07       0  4158.2     .12       0  4207.5    .035       0
  4477.9     .12       0  4990.9     .05       0  5024.6     .12       0
  5043.3    .035       0  5285.3     .12       0  5328.2     .07       0
Bank Sta=4990.9,5024.6
XS Rating Curve= 0 ,0
Exp/Cntr=0.3,0.1

Chan Stop Cuts=-1
Use User Specified Reach Order=0
Composite Channel Slope=5