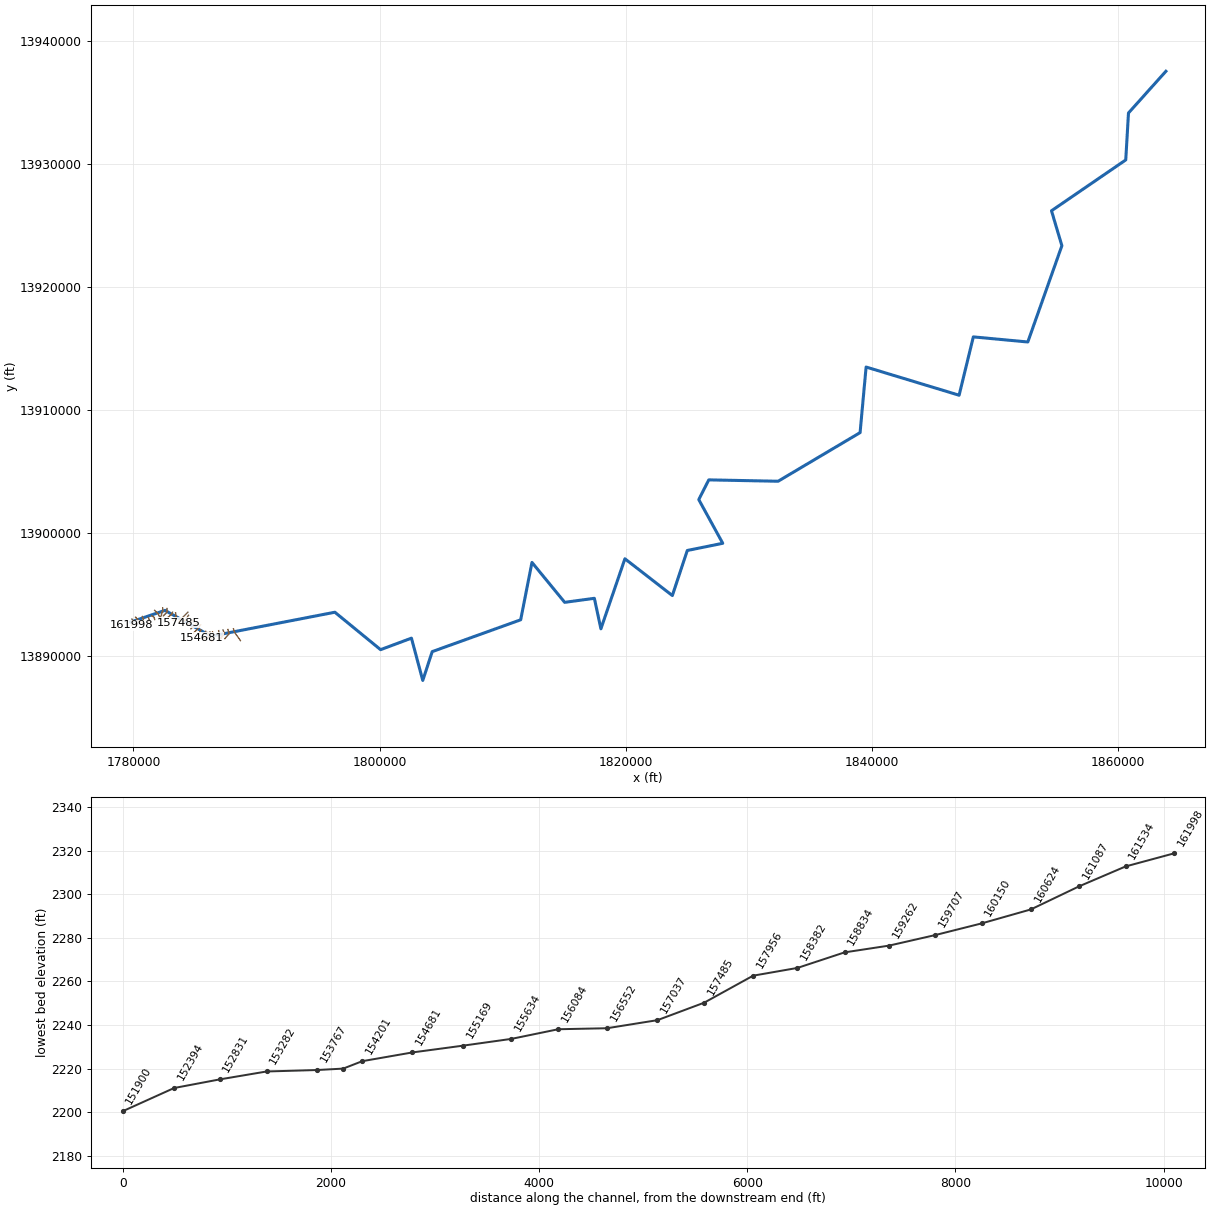
--- South Fork Guadalupe River.prj (project) ---

Proj Title=South Fork Guadalupe River Base Level Engineering
Current Plan=p01
Default Exp/Contr=0.3,0.1
English Units
Geom File=g01
Flow File=f01
Plan File=p01
Y Axis Title=Elevation
X Axis Title(PF)=Main Channel Distance
X Axis Title(XS)=Station
BEGIN DESCRIPTION:
South Fork Guadalupe River
END DESCRIPTION:
DSS Export Rating Curves= 0
DSS Export Rating Curve Sorted= 0
DSS Export Volume Flow Curves= 0
DXF OffsetX= 0
DXF OffsetY= 0
DXF ScaleX= 1
DXF ScaleY= 10

--- South Fork Guadalupe River.p01 (plan) ---

Plan Title=Multiple Run
Short Identifier=Multiple
Geom File=g01
Flow File=f01
Subcritical Flow
K Sum by GR= 0
Std Step Tol= 0.01
Critical Tol= 0.01
Num of Std Step Trials= 20
Max Error Tol= 0.3
Flow Tol Ratio= 0.001
Split Flow NTrial= 30
Split Flow Tol= 0.02
Split Flow Ratio= 0.02
Log Output Level= 0
Friction Slope Method= 1
Unsteady Friction Slope Method= 2
Unsteady Bridges Friction Slope Method= 1
Parabolic Critical Depth
Global Vel Dist=  1 , 1 , 1
Global Log Level= 0
CheckData=True
Encroach Param= -1, 0, 0, 0
BEGIN DESCRIPTION:
Multiple Run
END DESCRIPTION:

--- South Fork Guadalupe River.f01 (steady flow) ---

Flow Title=Multiple
Number of Profiles=7
Profile Names=10-year,25-year,50-year,1pct_min,100-year,1pct_plu,500-year
River Rch & RM= South Fork Guada,Reach-1,161998
    1348    2325    3263    2210    4409    8797    7966
River Rch & RM= South Fork Guada,Reach-1,156552
    1411    2434    3415    2312    4612    9202    8322
River Rch & RM= South Fork Guada,Reach-1,154018
    2620    4656    6662    4588    9155   18267   17120
River Rch & RM= South Fork Guada,Reach-1,150979
    3673    6619    9561    6641   13250   26437   25202
River Rch & RM= South Fork Guada,Reach-1,149135
    3959    7146   10333    7183   14331   28595   27301
River Rch & RM= South Fork Guada,Reach-1,146838
    4230    7649   11075    7705   15374   30675   29343
River Rch & RM= South Fork Guada,Reach-1,145903
    4365    7895   11433    7954   15871   31667   30290
River Rch & RM= South Fork Guada,Reach-1,144529
    4859    8813   12786    8910   17777   35470   34031
River Rch & RM= South Fork Guada,Reach-1,141701
    5335    9690   14069    9808   19569   39045   37492
River Rch & RM= South Fork Guada,Reach-1,137467
    5503    9990   14500   10103   20158   40220   38579
River Rch & RM= South Fork Guada,Reach-1,134573
    5453    9874   14305    9947   19847   39599   37830
River Rch & RM= South Fork Guada,Reach-1,128883
    6537   11901   17307   12074   24090   48067   46219
River Rch & RM= South Fork Guada,Reach-1,125554
    7245   13234   19289   13485   26906   53684   51831
River Rch & RM= South Fork Guada,Reach-1,124932
    7340   13392   19504   13622   27180   54231   52261
River Rch & RM= South Fork Guada,Reach-1,120690
    7443   13582   19785   13820   27574   55018   53031
River Rch & RM= South Fork Guada,Reach-1,119518
    8004   14612   21290   14871   29671   59202   57059
River Rch & RM= South Fork Guada,Reach-1,113435
    8666   15895   23227   16267   32458   64761   62772
River Rch & RM= South Fork Guada,Reach-1,106918
    8686   15918   23246   16269   32460   64767   62685
River Rch & RM= South Fork Guada,Reach-1,101406
    9138   16765   24504   17162   34242   68323   66223
River Rch & RM= South Fork Guada,Reach-1,97633
    9178   16836   24606   17232   34382   68602   66480
River Rch & RM= South Fork Guada,Reach-1,97064
    9305   17081   24975   17498   34913   69660   67562
River Rch & RM= South Fork Guada,Reach-1,94289
    9353   17155   25071   17555   35026   69886   67702
River Rch & RM= South Fork Guada,Reach-1,87419
   10255   18847   27580   19335   38578   76974   74739
River Rch & RM= South Fork Guada,Reach-1,83673
   11001   20196   29541   20700   41301   82407   79897
River Rch & RM= South Fork Guada,Reach-1,76197
   10560   19422   28438   19946   39798   79408   77178
River Rch & RM= South Fork Guada,Reach-1,74163
   12327   22683   33236   23324   46537   92853   90281
River Rch & RM= South Fork Guada,Reach-1,70663
   12519   23043   33769   23701   47290   94357   91768
River Rch & RM= South Fork Guada,Reach-1,69931
   12600   23190   33983   23850   47588   94950   92333
River Rch & RM= South Fork Guada,Reach-1,68050
   12674   23319   34163   23970   47827   95428   92745
River Rch & RM= South Fork Guada,Reach-1,63004
   13924   25669   37660   26457   52789  105327  102613
River Rch & RM= South Fork Guada,Reach-1,54693
   15037   27768   40788   28678   57221  114171  111370
River Rch & RM= South Fork Guada,Reach-1,52532
   15230   28133   41332   29065   57993  115711  112907
River Rch & RM= South Fork Guada,Reach-1,49139
   15335   28309   41574   29223   58308  116339  113419
River Rch & RM= South Fork Guada,Reach-1,42812
   16352   30232   44444   31271   62394  124492  121593
River Rch & RM= South Fork Guada,Reach-1,38610
   16514   30515   44844   31540   62931  125564  122540
River Rch & RM= South Fork Guada,Reach-1,32729
   18299   33884   49871   35124   70082  139832  136823
River Rch & RM= South Fork Guada,Reach-1,27965
   18291   33854   49813   35073   69979  139626  136537
River Rch & RM= South Fork Guada,Reach-1,23223
   18690   34605   50931   35868   71566  142793  139692
River Rch & RM= South Fork Guada,Reach-1,18866
   19119   35396   52094   36685   73195  146044  142846
River Rch & RM= South Fork Guada,Reach-1,13984
   19933   36811   54098   38041   75901  151443  147627
River Rch & RM= South Fork Guada,Reach-1,9670
   19926   36777   54027   37976   75771  151183  147250
River Rch & RM= South Fork Guada,Reach-1,5155
   19892   36699   53897   37873   75567  150775  146766
River Rch & RM= South Fork Guada,Reach-1,2819
   20014   36940   54268   38146   76111  151862  147917
Boundary for River Rch & Prof#=South Fork Guada,Reach-1,1
Up Type=0
Dn Type=3
Dn Slope=0.005
Boundary for River Rch & Prof#=South Fork Guada,Reach-1,2
Up Type=0
Dn Type=3
Dn Slope=0.005
Boundary for River Rch & Prof#=South Fork Guada,Reach-1,3
Up Type=0
Dn Type=3
Dn Slope=0.005
Boundary for River Rch & Prof#=South Fork Guada,Reach-1,4
Up Type=0
Dn Type=3
Dn Slope=0.005
Boundary for River Rch & Prof#=South Fork Guada,Reach-1,5
Up Type=0
Dn Type=3
Dn Slope=0.005
Boundary for River Rch & Prof#=South Fork Guada,Reach-1,6
Up Type=0
Dn Type=3
Dn Slope=0.005
Boundary for River Rch & Prof#=South Fork Guada,Reach-1,7
Up Type=0
Dn Type=3
Dn Slope=0.005

--- South Fork Guadalupe River.g01 (geometry) ---

Geom Title=Existing Conditions
Program Version=4.10

River Reach=South Fork Guada,Reach-1
Reach XY= 30
        1779775.       13892725.      1782564.52     13893674.07
      1786300.32     13891574.72       1796364.5     13893523.78
      1800076.46     13890478.53       1802584.8     13891414.52
      1803504.87     13887974.57      1804272.57     13890319.48
      1811458.59     13892908.07        1812375.       13897575.
      1815033.48     13894328.49      1817445.08     13894655.21
        1817975.       13892175.      1819926.49     13897871.41
      1823777.45     13894880.46      1824994.78     13898545.09
      1827873.49     13899130.87      1825925.93     13902685.48
      1826738.39     13904288.68      1832369.13      13904177.1
      1839031.05     13908133.16      1839518.87     13913467.12
        1847075.       13911175.      1848230.46     13915919.78
      1852655.36     13915504.53       1855423.8      13923335.5
      1854580.73     13926177.55      1860611.36     13930311.64
      1860834.13     13934131.74        1863875.       13937525.

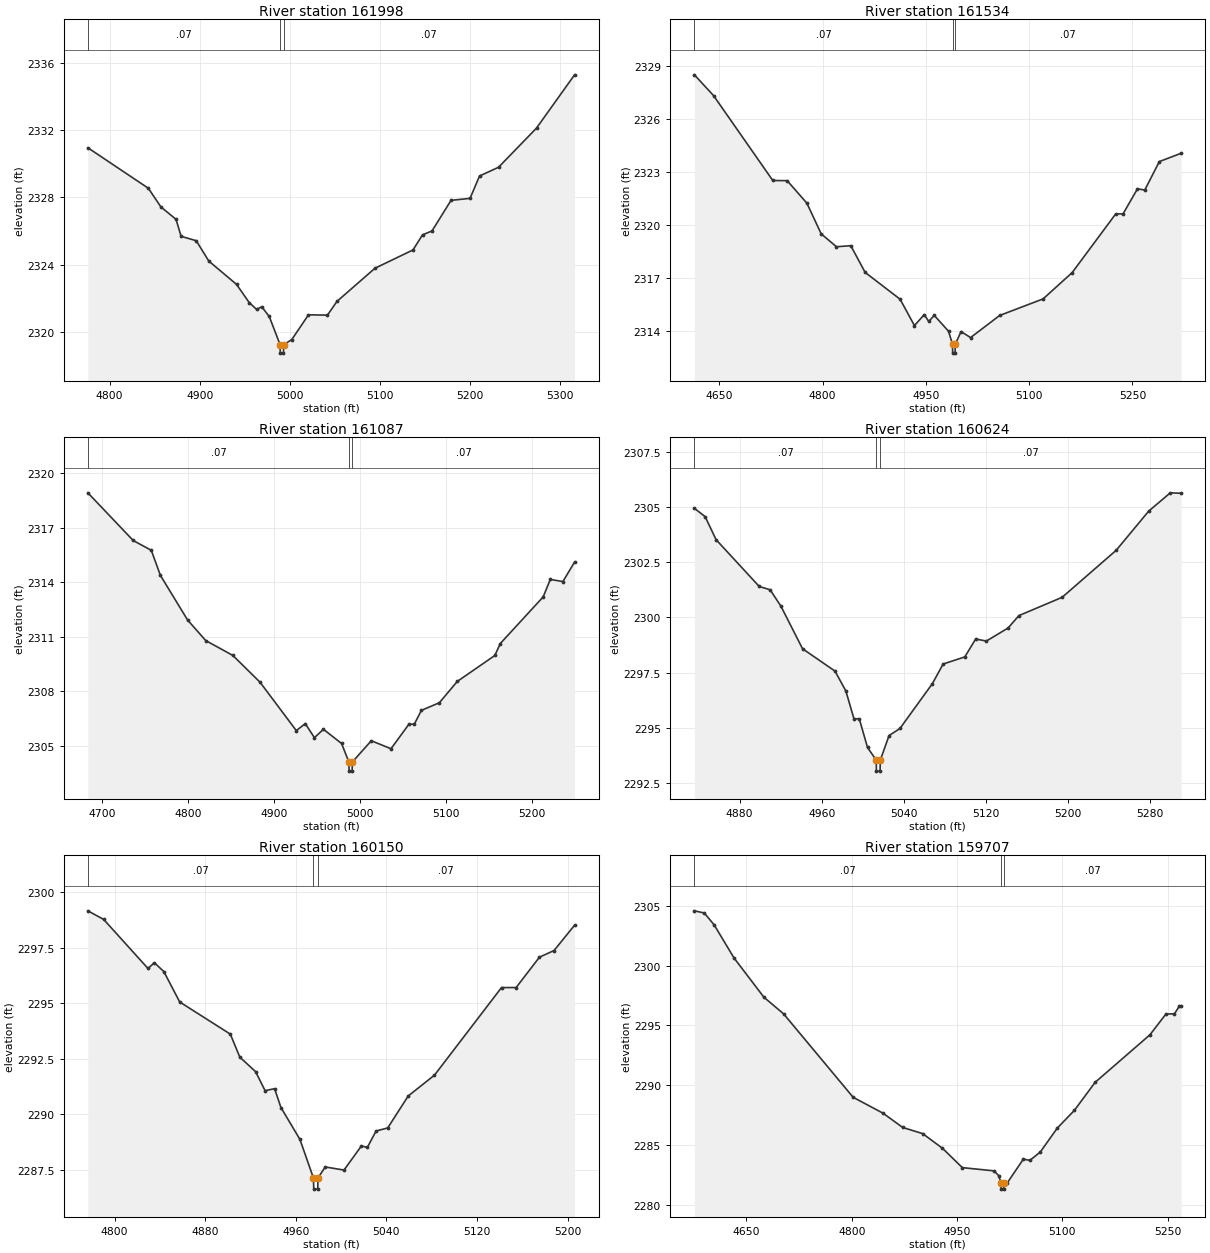
Type RM Length L Ch R = 1 ,161998  ,464,464,464
BEGIN DESCRIPTION:
South Fork Guadalupe River 267.0
END DESCRIPTION:
XS GIS Cut Line= 3
      1779875.01     13892974.97        1779975.       13892775.
        1779875.     13892475.01
#Sta/Elev= 30
    4776 2330.95  4843.1 2328.54    4857 2327.43  4873.8 2326.69  4879.4 2325.68
  4896.2 2325.42  4910.1 2324.21  4940.9 2322.82  4954.9 2321.74  4963.2 2321.33
  4968.8 2321.49  4977.2 2320.91  4989.2 2319.23  4989.4 2318.73  4992.9 2318.73
  4993.2 2319.23  5002.2 2319.54  5020.7 2321.01  5041.7 2320.99  5052.3 2321.81
  5094.4 2323.78  5136.6 2324.87  5147.2 2325.77  5157.7    2326  5178.8 2327.82
  5199.9 2327.94  5210.4 2329.27  5231.5 2329.79  5273.6 2332.12  5315.8 2335.29
#Mann= 3 ,-1 , 0
    4776     .07       0  4989.2     .05       0  4993.2     .07       0
Bank Sta=4989.2,4993.2
XS Rating Curve= 0 ,0
Exp/Cntr=0.3,0.1

Type RM Length L Ch R = 1 ,161534  ,447,447,447
BEGIN DESCRIPTION:
South Fork Guadalupe River 266.0
END DESCRIPTION:
XS GIS Cut Line= 3
      1780175.03     13893124.96        1780425.       13892825.
        1780325.     13892524.99
#Sta/Elev= 30
  4613.9  2328.5  4641.8 2327.32  4727.7 2322.52  4748.6 2322.51  4777.2 2321.24
    4798  2319.5  4820.2 2318.77    4841 2318.83  4861.8 2317.32  4912.6  2315.8
  4933.4 2314.31  4947.7 2314.93  4954.2 2314.54  4962.1 2314.89  4982.9 2313.99
  4988.7 2313.25  4988.9 2312.75  4992.4 2312.75  4992.7 2313.25  5001.1 2313.97
  5014.9 2313.63  5057.1 2314.88  5120.3 2315.82  5162.5 2317.31  5225.7 2320.63
  5236.3 2320.63  5257.3 2322.05  5267.9 2321.98    5289 2323.59  5320.6 2324.06
#Mann= 3 ,-1 , 0
  4613.9     .07       0  4988.7     .05       0  4992.7     .07       0
Bank Sta=4988.7,4992.7
XS Rating Curve= 0 ,0
Exp/Cntr=0.3,0.1

Type RM Length L Ch R = 1 ,161087  ,463,463,463
BEGIN DESCRIPTION:
South Fork Guadalupe River 265.0
END DESCRIPTION:
XS GIS Cut Line= 3
      1780724.99     13893175.04        1780825.       13892875.
      1780674.98     13892674.97
#Sta/Elev= 30
  4683.7 2318.92  4736.4  2316.3  4757.5 2315.76  4768.1 2314.38  4799.7 2311.93
  4820.8  2310.8  4852.4 2309.98    4884 2308.51  4926.2 2305.85  4936.7 2306.23
  4947.3 2305.46  4957.8 2305.92  4978.9 2305.14  4987.4 2304.12  4987.7 2303.62
  4991.2 2303.62  4991.4 2304.12  5013.5 2305.29  5036.4 2304.85  5057.3  2306.2
  5063.5  2306.2  5071.8 2306.96  5092.7 2307.38  5113.5 2308.55  5157.3 2309.98
  5163.5 2310.63  5213.5  2313.2  5221.8 2314.16  5236.4 2314.04    5250 2315.11
#Mann= 3 ,-1 , 0
  4683.7     .07       0  4987.4     .05       0  4991.4     .07       0
Bank Sta=4987.4,4991.4
XS Rating Curve= 0 ,0
Exp/Cntr=0.3,0.1

Type RM Length L Ch R = 1 ,160624  ,474,474,474
BEGIN DESCRIPTION:
South Fork Guadalupe River 264.0
END DESCRIPTION:
XS GIS Cut Line= 3
        1781225.       13893075.        1781275.       13892925.
      1781175.01     13892625.04
#Sta/Elev= 30
    4836 2304.94  4846.5 2304.56  4857.1 2303.52  4899.2  2301.4  4909.8 2301.25
  4920.3 2300.51  4941.4 2298.58    4973 2297.57  4983.6 2296.67  4991.5 2295.41
  4996.7 2295.41  5004.7 2294.11  5013.2 2293.54  5013.4 2293.04  5016.9 2293.04
  5017.2 2293.54  5025.7 2294.65  5036.3 2294.97  5067.9    2297  5078.4 2297.89
  5099.5 2298.21  5110.1 2299.02  5120.6 2298.93  5141.7 2299.52  5152.2 2300.08
  5194.4 2300.91  5247.1 2303.04  5278.7 2304.81  5299.8 2305.64  5310.3 2305.62
#Mann= 3 ,-1 , 0
    4836     .07       0  5013.2     .05       0  5017.2     .07       0
Bank Sta=5013.2,5017.2
XS Rating Curve= 0 ,0
Exp/Cntr=0.3,0.1

Type RM Length L Ch R = 1 ,160150  ,443,443,443
BEGIN DESCRIPTION:
South Fork Guadalupe River 263.0
END DESCRIPTION:
XS GIS Cut Line= 3
      1781475.01       13893225.        1781675.       13893125.
      1781725.01     13892924.96
#Sta/Elev= 30
  4776.4 2299.17  4790.4 2298.78  4829.5 2296.57  4835.1 2296.83  4843.5 2296.43
  4857.5 2295.06  4902.2 2293.61  4910.6 2292.57  4924.5 2291.92  4932.9 2291.06
  4941.3 2291.15  4946.9  2290.3  4963.7 2288.86  4975.6 2287.12  4975.9 2286.62
  4979.4 2286.62  4979.6 2287.12    4986 2287.62  5002.6 2287.48    5018 2288.57
  5023.2  2288.5  5030.9 2289.24  5041.2 2289.38  5059.3 2290.82  5082.5 2291.76
  5141.7 2295.71  5154.6 2295.71  5175.2 2297.08  5188.1 2297.38  5206.2 2298.52
#Mann= 3 ,-1 , 0
  4776.4     .07       0  4975.6     .05       0  4979.6     .07       0
Bank Sta=4975.6,4979.6
XS Rating Curve= 0 ,0
Exp/Cntr=0.3,0.1

Type RM Length L Ch R = 1 ,159707  ,445,445,445
BEGIN DESCRIPTION:
South Fork Guadalupe River 262.0
END DESCRIPTION:
XS GIS Cut Line= 3
      1781725.03     13893674.97        1782025.       13893375.
      1782125.01     13893124.98
#Sta/Elev= 30
  4575.8  2304.6  4589.9 2304.42    4604 2303.42  4632.3 2300.65  4674.8 2297.37
    4703 2295.97    4802 2288.99  4844.5 2287.66  4872.7 2286.46    4901 2285.95
  4929.3 2284.72  4957.6  2283.1  5002.7 2282.83  5009.4 2282.43  5012.8  2281.8
  5013.1  2281.3  5016.6  2281.3  5016.8  2281.8  5021.6 2281.82  5044.5 2283.81
  5053.9 2283.71  5068.7 2284.41  5092.9 2286.41  5117.2 2287.89  5146.8 2290.24
  5224.9 2294.22  5247.7 2295.96  5259.9 2295.98  5266.6  2296.6  5269.3  2296.6
#Mann= 3 ,-1 , 0
  4575.8     .07       0  5012.8     .05       0  5016.8     .07       0
Bank Sta=5012.8,5016.8
XS Rating Curve= 0 ,0
Exp/Cntr=0.3,0.1

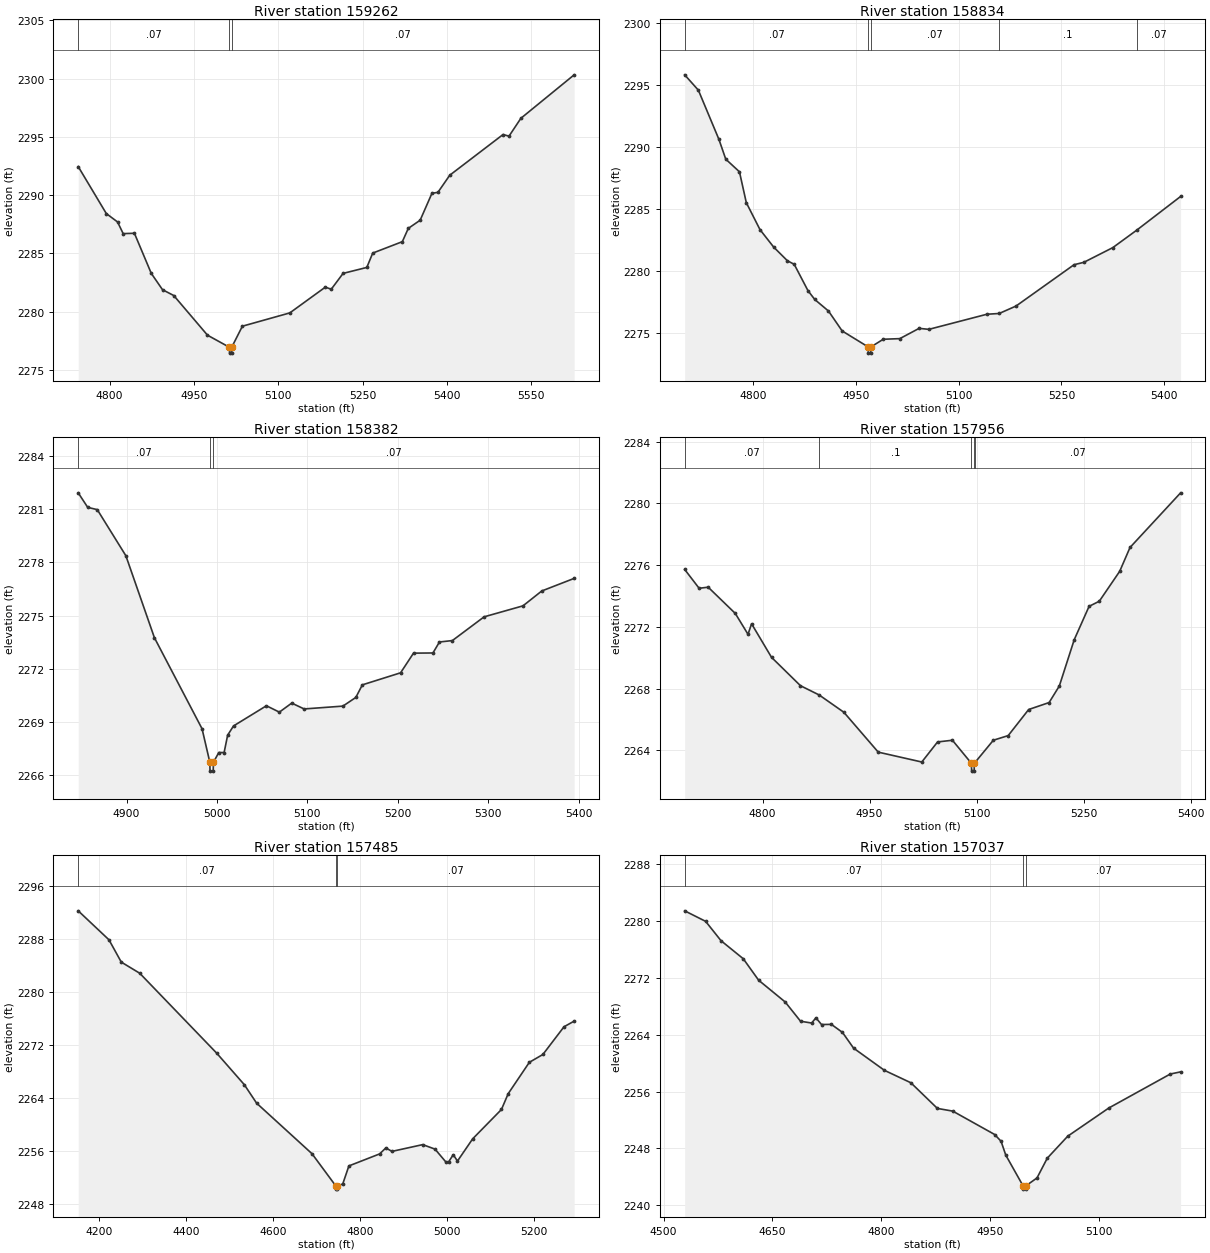
Type RM Length L Ch R = 1 ,159262  ,428,428,428
BEGIN DESCRIPTION:
South Fork Guadalupe River 261.0
END DESCRIPTION:
XS GIS Cut Line= 3
        1782375.     13893874.97        1782375.       13893625.
      1782175.01     13893025.02
#Sta/Elev= 30
  4744.1 2292.45  4794.1 2288.42  4814.1  2287.7  4824.1  2286.7  4844.1 2286.73
  4874.1 2283.29  4894.1 2281.89  4914.1 2281.39  4974.1 2277.99  5013.2 2276.95
  5013.4 2276.45  5016.9 2276.45  5017.2 2276.95  5036.2 2278.76  5120.6  2279.9
  5183.8 2282.11  5194.3 2281.93  5215.4 2283.29  5257.6  2283.8  5268.1 2285.03
  5320.8 2286.01  5331.4 2287.15  5352.5 2287.85  5373.5 2290.16  5384.1 2290.24
  5405.2 2291.71    5500  2295.2  5510.6 2295.06  5531.7 2296.59  5626.5 2300.32
#Mann= 3 ,-1 , 0
  4744.1     .07       0  5013.2     .05       0  5017.2     .07       0
Bank Sta=5013.2,5017.2
XS Rating Curve= 0 ,0
Exp/Cntr=0.3,0.1

Type RM Length L Ch R = 1 ,158834  ,452,452,452
BEGIN DESCRIPTION:
South Fork Guadalupe River 260.0
END DESCRIPTION:
XS GIS Cut Line= 3
        1782725.     13893825.01        1782725.       13893525.
      1782424.98     13893224.98
#Sta/Elev= 30
  4699.7 2295.81  4719.7 2294.57  4749.7  2290.6  4759.7    2289  4779.7 2287.98
  4789.7 2285.49  4809.7 2283.31  4829.7  2281.9  4849.7  2280.8  4859.7 2280.51
  4879.7 2278.39  4889.7 2277.67  4909.7 2276.74  4929.7 2275.13  4967.7 2273.84
    4968 2273.34  4971.5 2273.34  4971.7 2273.84  4989.7 2274.46  5013.9 2274.51
  5042.1 2275.34  5056.3 2275.26  5141.1 2276.48    5159 2276.54  5183.6 2277.14
  5268.4 2280.48  5282.6 2280.67    5325 2281.86  5359.7 2283.26    5424 2285.99
#Mann= 5 ,-1 , 0
  4699.7     .07       0  4967.7     .05       0  4971.7     .07       0
    5159      .1       0  5359.7     .07       0
Bank Sta=4967.7,4971.7
XS Rating Curve= 0 ,0
Exp/Cntr=0.3,0.1

Type RM Length L Ch R = 1 ,158382  ,426,426,426
BEGIN DESCRIPTION:
South Fork Guadalupe River 259.0
END DESCRIPTION:
XS GIS Cut Line= 3
      1783174.99     13893524.98        1783125.       13893375.
      1782825.01     13893125.01
#Sta/Elev= 30
  4846.5 2281.93    4857 2281.11  4867.6 2280.98  4899.2 2278.38  4930.8 2273.75
  4983.5 2268.61  4992.1 2266.72  4992.3 2266.22  4995.8 2266.22  4996.1 2266.72
    5002 2267.27  5007.9 2267.27  5011.8 2268.25  5018.3 2268.77  5054.7 2269.91
    5069 2269.55  5082.7 2270.06  5096.4 2269.73  5139.3 2269.89  5153.6 2270.38
  5160.8 2271.09  5203.1 2271.77  5217.4 2272.88  5238.9 2272.89  5246.1 2273.51
  5260.4 2273.59  5295.5 2274.93  5338.5 2275.55  5359.3 2276.39  5395.1  2277.1
#Mann= 3 ,-1 , 0
  4846.5     .07       0  4992.1     .05       0  4996.1     .07       0
Bank Sta=4992.1,4996.1
XS Rating Curve= 0 ,0
Exp/Cntr=0.3,0.1

Type RM Length L Ch R = 1 ,157956  ,471,471,471
BEGIN DESCRIPTION:
South Fork Guadalupe River 258.0
END DESCRIPTION:
XS GIS Cut Line= 3
      1783425.01     13893474.96        1783475.       13893175.
        1783225.       13892875.
#Sta/Elev= 30
    4691 2275.72  4711.2  2274.5  4723.9 2274.57  4761.9 2272.87  4779.7 2271.52
  4784.7  2272.2  4812.6 2270.03  4853.2 2268.19  4879.4 2267.59    4914 2266.47
  4962.1 2263.89  5023.1 2263.25  5045.2 2264.55    5066 2264.66  5092.7 2263.16
  5092.9 2262.66  5096.4 2262.66  5096.7 2263.16    5098 2263.24  5123.3 2264.66
  5144.1 2264.96  5172.8 2266.65  5201.4  2267.1  5215.7 2268.17  5236.6 2271.17
  5257.4 2273.33  5271.7 2273.66  5300.3  2275.6  5314.7 2277.14  5385.6 2280.68
#Mann= 5 ,-1 , 0
    4691     .07       0  4879.4      .1       0  5092.7     .05       0
  5096.7      .1       0    5098     .07       0
Bank Sta=5092.7,5096.7
XS Rating Curve= 0 ,0
Exp/Cntr=0.3,0.1

Type RM Length L Ch R = 1 ,157485  ,448,448,448
BEGIN DESCRIPTION:
South Fork Guadalupe River 257.0
END DESCRIPTION:
XS GIS Cut Line= 3
      1784424.97     13893524.97        1783825.       13892925.
      1783675.02     13892675.03
#Sta/Elev= 30
  4151.5 2292.22  4222.2 2287.85  4250.5 2284.49  4292.9 2282.81  4469.7 2270.77
  4533.3 2266.01  4561.6 2263.22  4688.9  2255.6  4743.4 2250.76  4743.7 2250.26
  4747.2 2250.26  4747.4 2250.76  4759.6 2251.04  4773.7 2253.76  4844.4 2255.57
  4858.6 2256.47  4872.7 2255.95  4943.4 2256.97  4971.7 2256.29  4996.4 2254.37
  5002.9 2254.37  5013.6 2255.45  5023.3 2254.49  5058.3 2257.85  5124.4 2262.27
  5139.9 2264.65  5188.5 2269.38  5219.6 2270.56  5268.2 2274.74  5291.5 2275.59
#Mann= 3 ,-1 , 0
  4151.5     .07       0  4743.4     .05       0  4747.4     .07       0
Bank Sta=4743.4,4747.4
XS Rating Curve= 0 ,0
Exp/Cntr=0.3,0.1

Type RM Length L Ch R = 1 ,157037  ,485,485,485
BEGIN DESCRIPTION:
South Fork Guadalupe River 256.0
END DESCRIPTION:
XS GIS Cut Line= 3
      1784475.01     13893275.02        1784225.       13892875.
      1784074.97     13892724.97
#Sta/Elev= 30
  4529.2 2281.41  4558.1 2279.93  4579.3 2277.21    4610 2274.67  4631.2 2271.65
  4667.8 2268.59    4689 2265.88  4704.3 2265.63  4710.2 2266.36  4717.9 2265.42
  4731.5 2265.44  4746.8 2264.31  4762.1  2262.1  4804.6 2258.98  4841.1 2257.23
  4877.7 2253.62  4898.9 2253.24  4956.7 2249.95  4965.5    2249    4972 2247.05
  4995.6 2242.77    4996 2242.27    5000 2242.27  5000.3 2242.77  5015.1 2243.85
  5029.2 2246.62  5057.5 2249.72  5114.1 2253.68  5198.9 2258.46  5213.1 2258.76
#Mann= 3 ,-1 , 0
  4529.2     .07       0  4995.6     .05       0  5000.3     .07       0
Bank Sta=4995.6,5000.3
XS Rating Curve= 0 ,0
Exp/Cntr=0.3,0.1

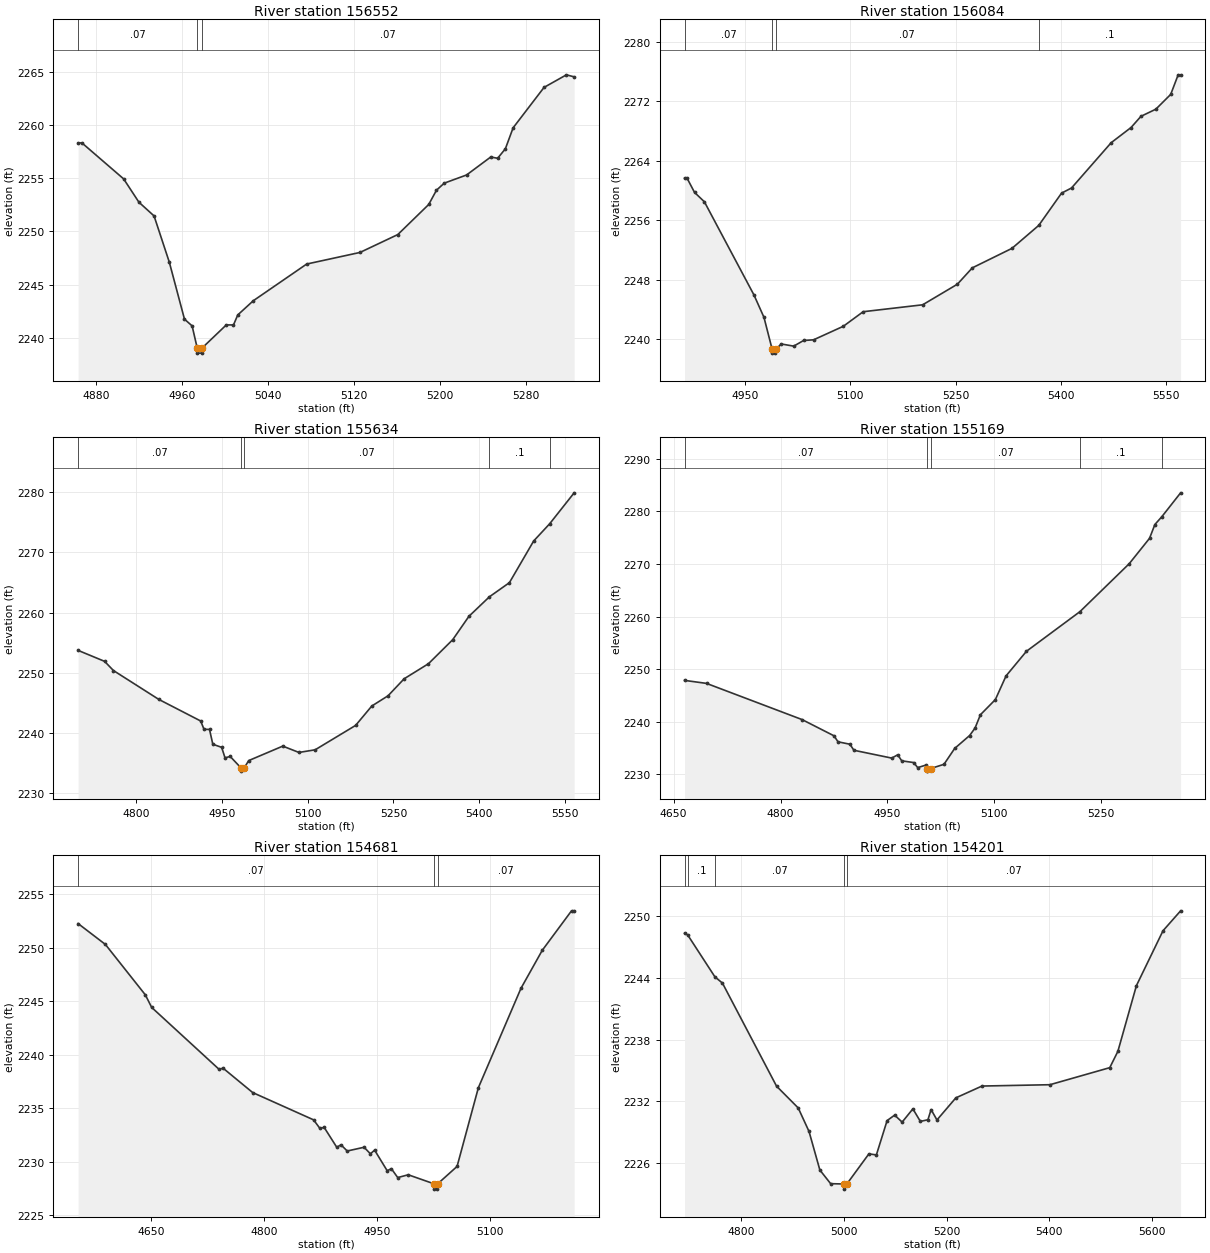
Type RM Length L Ch R = 1 ,156552  ,468,468,468
BEGIN DESCRIPTION:
South Fork Guadalupe River 255.0
END DESCRIPTION:
XS GIS Cut Line= 3
      1784775.01     13892875.01        1784675.       13892775.
        1784475.       13892525.
#Sta/Elev= 30
  4863.2 2258.31  4866.8 2258.31  4905.6 2254.93  4919.8 2252.74  4933.9 2251.45
  4948.1  2247.1  4962.2 2241.75  4969.3 2241.12    4974 2239.06  4974.3 2238.56
  4978.4 2238.56  4978.8 2239.06  5001.1 2241.21  5007.8 2241.21  5011.8 2242.15
  5026.2 2243.48  5075.9 2246.93  5125.5 2248.02  5160.7  2249.7  5189.5 2252.53
  5196.7 2253.87  5203.9 2254.53  5224.7  2255.3  5247.2 2256.99  5253.6 2256.87
  5260.8 2257.76    5268 2259.73  5296.8 2263.53  5317.6 2264.71  5324.8 2264.52
#Mann= 3 ,-1 , 0
  4863.2     .07       0    4974     .05       0  4978.8     .07       0
Bank Sta=4974,4978.8
XS Rating Curve= 0 ,0
Exp/Cntr=0.3,0.1

Type RM Length L Ch R = 1 ,156084  ,450,450,450
BEGIN DESCRIPTION:
South Fork Guadalupe River 254.0
END DESCRIPTION:
XS GIS Cut Line= 3
      1785175.02     13892675.02        1785075.       13892575.
      1784675.03     13892175.03
#Sta/Elev= 30
  4863.6 2261.62  4867.2 2261.62  4877.8 2259.72  4891.9 2258.45  4962.6 2245.91
  4976.8 2242.91  4988.5  2238.6  4988.9  2238.1    4993  2238.1  4993.3  2238.6
  5001.5 2239.33  5019.2 2239.04  5033.3  2239.8  5047.5 2239.89  5089.9 2241.71
  5118.2 2243.67    5203  2244.6  5252.5 2247.37  5273.8 2249.57  5330.3 2252.19
  5368.5 2255.28    5401 2259.62  5415.2 2260.31  5471.7  2266.4    5500 2268.44
  5514.2 2269.95  5535.4 2270.91  5556.6  2272.9  5567.2 2275.53  5570.7 2275.53
#Mann= 4 ,-1 , 0
  4863.6     .07       0  4988.5     .05       0  4993.3     .07       0
  5368.5      .1       0
Bank Sta=4988.5,4993.3
XS Rating Curve= 0 ,0
Exp/Cntr=0.3,0.1

Type RM Length L Ch R = 1 ,155634  ,465,465,465
BEGIN DESCRIPTION:
South Fork Guadalupe River 253.0
END DESCRIPTION:
XS GIS Cut Line= 3
       1785433.3     13892481.06        1785275.       13892225.
      1784875.02     13891825.02
#Sta/Elev= 30
    4699 2253.72  4745.3  2251.9  4760.7 2250.38  4839.9 2245.59  4913.2    2242
    4919 2240.62  4928.6  2240.6  4934.4 2238.14  4949.8 2237.63  4955.7 2235.89
  4964.8 2236.11    4984 2234.18  4984.4 2233.68    4989 2234.18  4997.1 2235.43
  5056.6 2237.83  5084.9 2236.78  5113.2 2237.22  5183.9 2241.27  5212.2 2244.49
  5240.5 2246.18  5268.7 2249.01  5311.2 2251.51  5353.6  2255.5  5381.9 2259.38
  5417.6 2262.61  5452.6 2264.96    5495 2271.88    5523 2274.74  5565.7 2279.87
#Mann= 5 ,-1 , 0
    4699     .07       0    4984     .05       0    4989     .07       0
  5417.6      .1       0    5523     .07       0
Bank Sta=4984,4989
XS Rating Curve= 0 ,0
Exp/Cntr=0.3,0.1

Type RM Length L Ch R = 1 ,155169  ,488,488,488
BEGIN DESCRIPTION:
South Fork Guadalupe River 252.0
END DESCRIPTION:
XS GIS Cut Line= 3
      1785475.02     13892075.03        1785325.       13891775.
        1785025.       13891575.
#Sta/Elev= 30
  4665.3 2247.84  4696.1 2247.27  4830.2 2240.38    4875 2237.29  4880.6 2236.15
  4897.3 2235.69  4902.9 2234.54    4956 2233.05  4964.4 2233.68    4970 2232.53
  4986.8  2232.2  4992.4 2231.24  5003.7 2231.71  5005.8 2231.07  5006.1 2230.57
  5010.8 2231.07  5029.3 2231.87  5044.3 2234.89  5065.3 2237.35  5072.9 2238.77
  5080.4  2241.3  5101.4 2244.19  5116.4  2248.7    5145 2253.38    5220 2260.92
  5289.2 2270.05  5317.7 2274.88  5325.2 2277.51  5335.1 2279.02  5361.3 2283.54
#Mann= 5 ,-1 , 0
  4665.3     .07       0  5005.8     .05       0  5010.8     .07       0
    5220      .1       0  5335.1     .07       0
Bank Sta=5005.8,5010.8
XS Rating Curve= 0 ,0
Exp/Cntr=0.3,0.1

Type RM Length L Ch R = 1 ,154681  ,480,480,480
BEGIN DESCRIPTION:
South Fork Guadalupe River 251.0
END DESCRIPTION:
XS GIS Cut Line= 3
      1785874.98     13891974.97        1785675.       13891575.
      1785525.01     13891425.01
#Sta/Elev= 30
  4552.8 2252.25  4589.1  2250.3  4642.2 2245.59  4650.6 2244.42    4740 2238.65
  4745.6 2238.74  4784.8 2236.47  4865.8 2233.92  4874.2 2233.12  4879.8 2233.22
  4896.6 2231.36  4902.2 2231.59  4910.5 2231.01  4932.9 2231.36  4941.3 2230.75
  4946.9 2231.09  4963.6 2229.17  4969.2 2229.36  4977.6 2228.53  4991.6 2228.79
  5025.7 2227.95  5026.1 2227.45  5030.4 2227.45  5030.8 2227.95  5056.5 2229.57
  5084.8 2236.92  5141.4  2246.2  5169.7 2249.75  5208.6 2253.44  5212.1 2253.44
#Mann= 3 ,-1 , 0
  4552.8     .07       0  5025.7     .05       0  5030.8     .07       0
Bank Sta=5025.7,5030.8
XS Rating Curve= 0 ,0
Exp/Cntr=0.3,0.1

Type RM Length L Ch R = 1 ,154201  ,183,183,183
BEGIN DESCRIPTION:
South Fork Guadalupe River 250.0
END DESCRIPTION:
XS GIS Cut Line= 4
      1786024.99     13891875.03        1786125.       13891575.
       1786021.2     13891433.61      1785555.04     13891343.77
#Sta/Elev= 30
  4689.5 2248.36  4695.5 2248.19  4748.7  2244.1  4763.3  2243.5  4868.7 2233.47
  4910.9 2231.35    4932 2229.06  4953.1 2225.31  4974.1 2223.98  5000.6 2223.95
    5001 2223.45  5005.7 2223.95  5048.6 2226.88  5063.2 2226.78  5084.1 2230.12
  5098.8 2230.65  5113.4 2229.97  5134.3 2231.26  5148.9 2230.04  5163.6  2230.2
  5169.8 2231.19  5181.2 2230.18    5218 2232.33  5268.9 2233.48  5401.3 2233.61
  5517.9 2235.27  5533.7 2236.86  5569.8 2243.25  5621.6 2248.59  5655.9 2250.53
#Mann= 5 ,-1 , 0
  4689.5     .07       0  4695.5      .1       0  4748.7     .07       0
  5000.6     .05       0  5005.7     .07       0
Bank Sta=5000.6,5005.7
XS Rating Curve= 0 ,0
Exp/Cntr=0.3,0.1

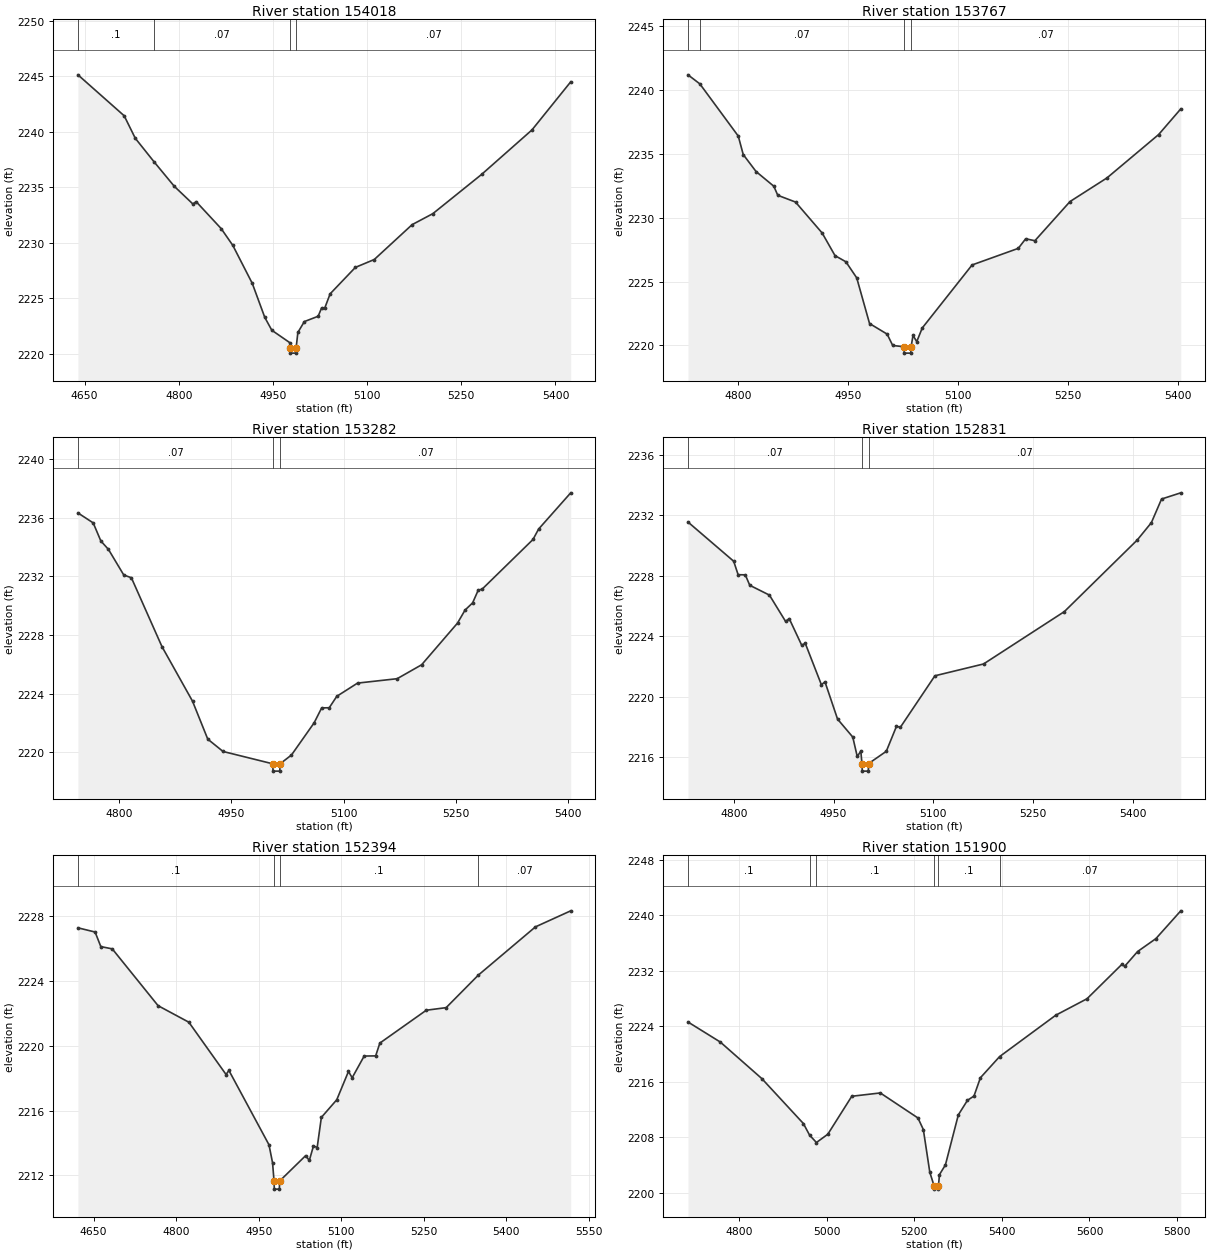
Type RM Length L Ch R = 1 ,154018  ,251,251,251
BEGIN DESCRIPTION:
South Fork Guadalupe River 249.1
END DESCRIPTION:
XS GIS Cut Line= 3
      1786211.32     13891923.15      1786312.87      13891546.9
      1786351.93     13891153.65
#Sta/Elev= 30
  4639.4 2245.11  4713.1 2241.42  4730.7  2239.4  4760.9 2237.26  4792.9 2235.07
  4822.5 2233.48  4827.7 2233.69  4867.6 2231.26  4886.1 2229.75  4917.1 2226.33
    4937 2223.27  4948.2 2222.11  4976.9 2220.99  4977.2 2220.55  4977.7 2220.05
  4986.5 2220.05    4987 2220.55  4989.7 2221.91    5000 2222.89    5022 2223.37
  5027.5 2224.12  5032.6 2224.12  5041.1 2225.39  5081.3 2227.77  5111.4 2228.48
  5171.7 2231.62  5204.7 2232.61  5282.3 2236.14  5362.6 2240.15  5424.3 2244.48
#Mann= 4 ,-1 , 0
  4639.4      .1       0  4760.9     .07       0  4977.2     .05       0
    4987     .07       0
Bank Sta=4977.2,4987
XS Rating Curve= 0 ,0
Exp/Cntr=0.3,0.1

Type RM Length L Ch R = 1 ,153767  ,485,485,485
BEGIN DESCRIPTION:
South Fork Guadalupe River 249.0
END DESCRIPTION:
XS GIS Cut Line= 3
      1786425.01     13891924.97        1786525.       13891675.
      1786475.01     13891275.04
#Sta/Elev= 30
  4731.2 2241.21  4747.4  2240.5  4799.8 2236.41  4806.6 2234.96  4824.1 2233.63
  4848.3 2232.48  4853.7 2231.77  4877.9 2231.24  4914.3 2228.81  4931.8 2227.04
  4946.6 2226.56  4961.4  2225.3  4978.9 2221.72  5002.9 2220.89  5010.5    2220
  5025.8  2219.9  5026.3  2219.4  5035.1  2219.4  5035.6  2219.9  5038.2 2220.79
  5043.3  2220.3  5050.8 2221.37  5118.8 2226.31  5181.8 2227.61  5191.9 2228.36
  5204.5 2228.21  5252.4 2231.28  5302.8 2233.13  5373.3 2236.53  5403.5 2238.54
#Mann= 4 ,-1 , 0
  4731.2      .1       0  4747.4     .07       0  5025.8     .05       0
  5035.6     .07       0
Bank Sta=5025.8,5035.6
XS Rating Curve= 0 ,0
Exp/Cntr=0.3,0.1

Type RM Length L Ch R = 1 ,153282  ,451,451,451
BEGIN DESCRIPTION:
South Fork Guadalupe River 248.0
END DESCRIPTION:
XS GIS Cut Line= 3
        1786925.     13892025.01        1786975.       13891775.
        1787025.     13891374.98
#Sta/Elev= 30
    4745 2236.33  4765.4 2235.65  4775.6 2234.42  4785.8 2233.84  4806.2  2232.1
  4816.4 2231.91  4857.2 2227.22    4898  2223.5  4918.4 2220.91  4938.8 2220.07
  5005.1 2219.23  5005.6 2218.73  5014.5 2218.73    5015 2219.23  5030.2 2219.83
  5060.4 2222.02  5070.5 2223.04  5080.6 2223.05  5090.7 2223.83  5118.4 2224.73
  5171.3 2225.03    5204 2225.98  5251.9 2228.82    5262 2229.71  5272.1  2230.2
  5279.6 2231.07  5284.7 2231.13  5352.7 2234.52  5360.2 2235.23  5403.1  2237.7
#Mann= 3 ,-1 , 0
    4745     .07       0  5005.1     .05       0    5015     .07       0
Bank Sta=5005.1,5015
XS Rating Curve= 0 ,0
Exp/Cntr=0.3,0.1

Type RM Length L Ch R = 1 ,152831  ,437,437,437
BEGIN DESCRIPTION:
South Fork Guadalupe River 247.0
END DESCRIPTION:
XS GIS Cut Line= 3
      1787274.99     13892075.03        1787375.       13891825.
        1787125.       13891425.
#Sta/Elev= 30
  4731.1 2231.55  4799.8 2228.96  4806.5 2228.07  4817.3 2228.06    4824 2227.37
  4853.6 2226.72  4877.9 2224.98  4883.3 2225.17  4902.1 2223.41  4907.5 2223.53
  4931.7  2220.8  4937.1 2220.99    4956 2218.53  4978.9 2217.34  4985.6 2216.06
    4991 2216.41  4992.7 2215.59  4993.2 2215.09  5002.2 2215.09  5002.7 2215.59
  5029.3  2216.4  5044.6 2218.05  5050.5 2217.99  5102.4 2221.39  5175.5 2222.17
    5297 2225.63  5406.6 2230.36  5427.9 2231.51  5443.2 2233.07  5472.1 2233.48
#Mann= 3 ,-1 , 0
  4731.1     .07       0  4992.7     .05       0  5002.7     .07       0
Bank Sta=4992.7,5002.7
XS Rating Curve= 0 ,0
Exp/Cntr=0.3,0.1

Type RM Length L Ch R = 1 ,152394  ,494,494,494
BEGIN DESCRIPTION:
South Fork Guadalupe River 246.0
END DESCRIPTION:
XS GIS Cut Line= 3
      1787674.99     13892125.05        1787775.       13891775.
      1787424.97     13891374.97
#Sta/Elev= 30
  4621.6 2227.29  4652.8 2227.03  4663.2 2226.13    4684 2225.99  4767.3 2222.48
  4823.2 2221.46  4890.8 2218.23    4896 2218.48  4968.8 2213.89  4975.3 2212.78
    4978 2211.65  4978.5 2211.15  4987.7 2211.15  4988.2 2211.65  5035.5 2213.22
  5042.1 2212.92  5049.7 2213.82  5056.4 2213.72    5064 2215.58    5092 2216.67
  5113.3 2218.42    5120 2218.03  5141.8 2219.37  5162.7 2219.38  5170.3 2220.17
  5254.7  2222.2  5290.8 2222.36  5349.3 2224.37  5453.1 2227.35  5517.2 2228.34
#Mann= 4 ,-1 , 0
  4621.6      .1       0    4978     .05       0  4988.2      .1       0
  5349.3     .07       0
Bank Sta=4978,4988.2
XS Rating Curve= 0 ,0
Exp/Cntr=0.3,0.1

Type RM Length L Ch R = 1 ,151900  ,470,470,470
BEGIN DESCRIPTION:
South Fork Guadalupe River 245.0
END DESCRIPTION:
XS GIS Cut Line= 3
      1788125.01     13892174.98        1788225.       13891875.
      1788694.96     13891216.51
#Sta/Elev= 30
  4683.3  2224.6  4757.1 2221.71  4851.9 2216.44  4946.8 2209.96    4961 2208.28
  4976.6 2207.22  5002.6 2208.42  5057.3 2213.89  5122.4 2214.37  5208.4 2210.76
  5220.7 2209.09  5235.5 2202.92  5245.1    2201  5245.6  2200.5  5254.8  2200.5
  5255.3    2201  5257.5 2202.59  5271.1 2203.99  5300.6 2211.21  5321.5 2213.31
  5336.3 2213.92    5351 2216.56  5394.8 2219.61  5523.1 2225.58  5594.4 2227.95
  5674.3 2232.93  5680.4 2232.63  5709.9 2234.76  5751.7 2236.62  5808.5 2240.63
#Mann= 6 ,-1 , 0
  4683.3      .1       0    4961     .07       0  4976.6      .1       0
  5245.1     .05       0  5255.3      .1       0  5394.8     .07       0
Bank Sta=5245.1,5255.3
XS Rating Curve= 0 ,0
Exp/Cntr=0.3,0.1