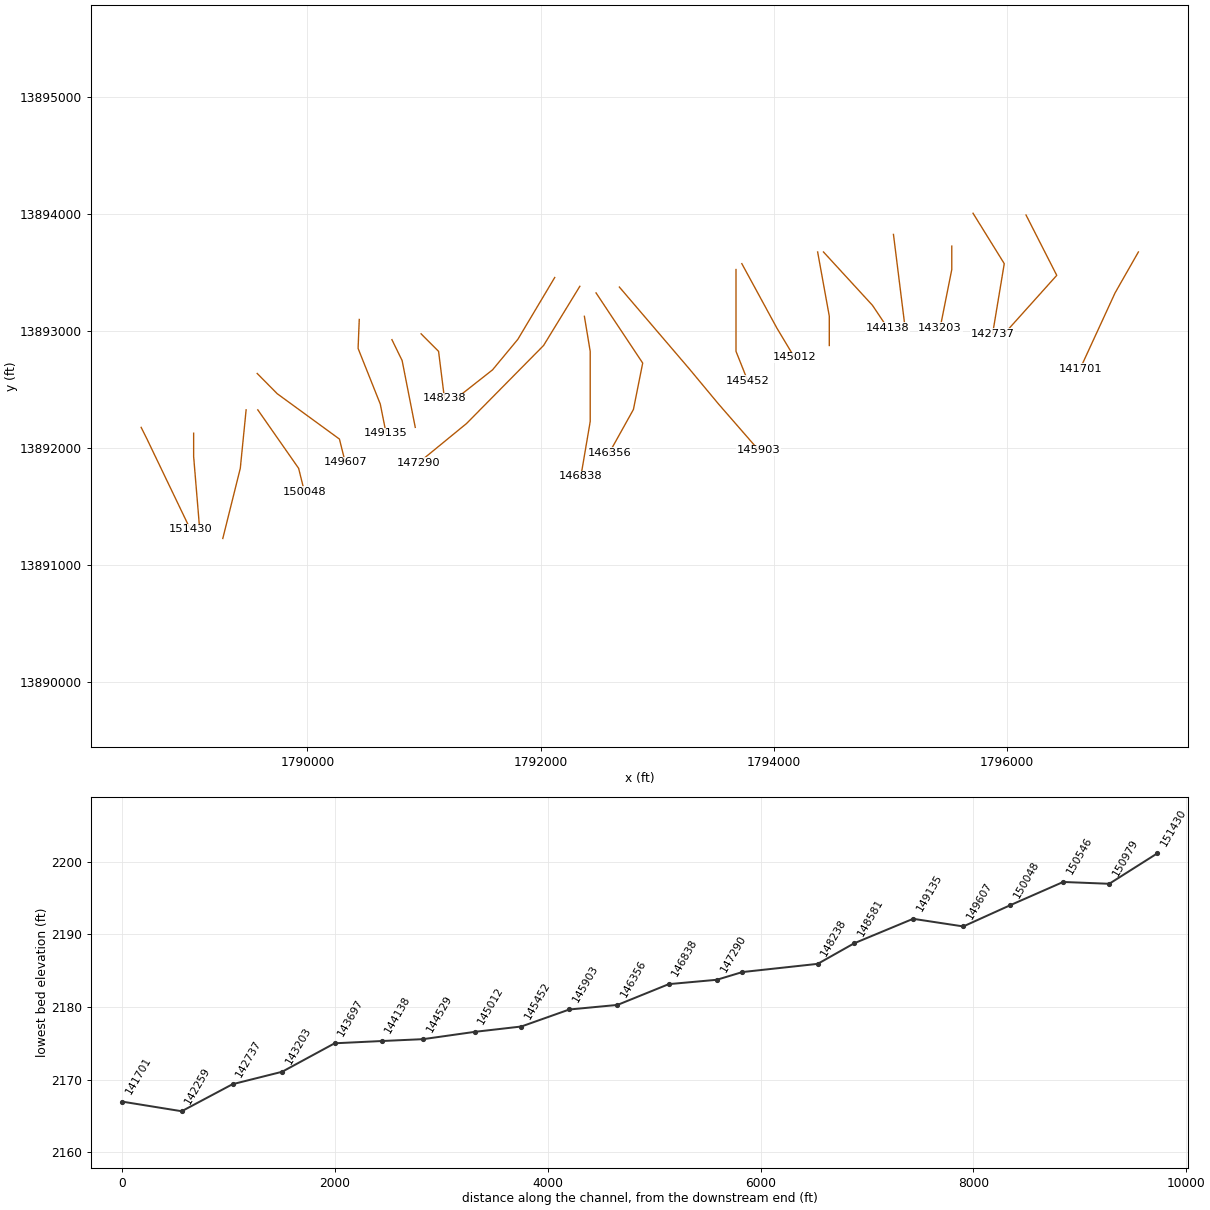
HEC-RAS study South Fork Guadalupe River.prj: South Fork Guadalupe River Base Level Engineering

--- South Fork Guadalupe River.g01 (geometry) --- (continued)

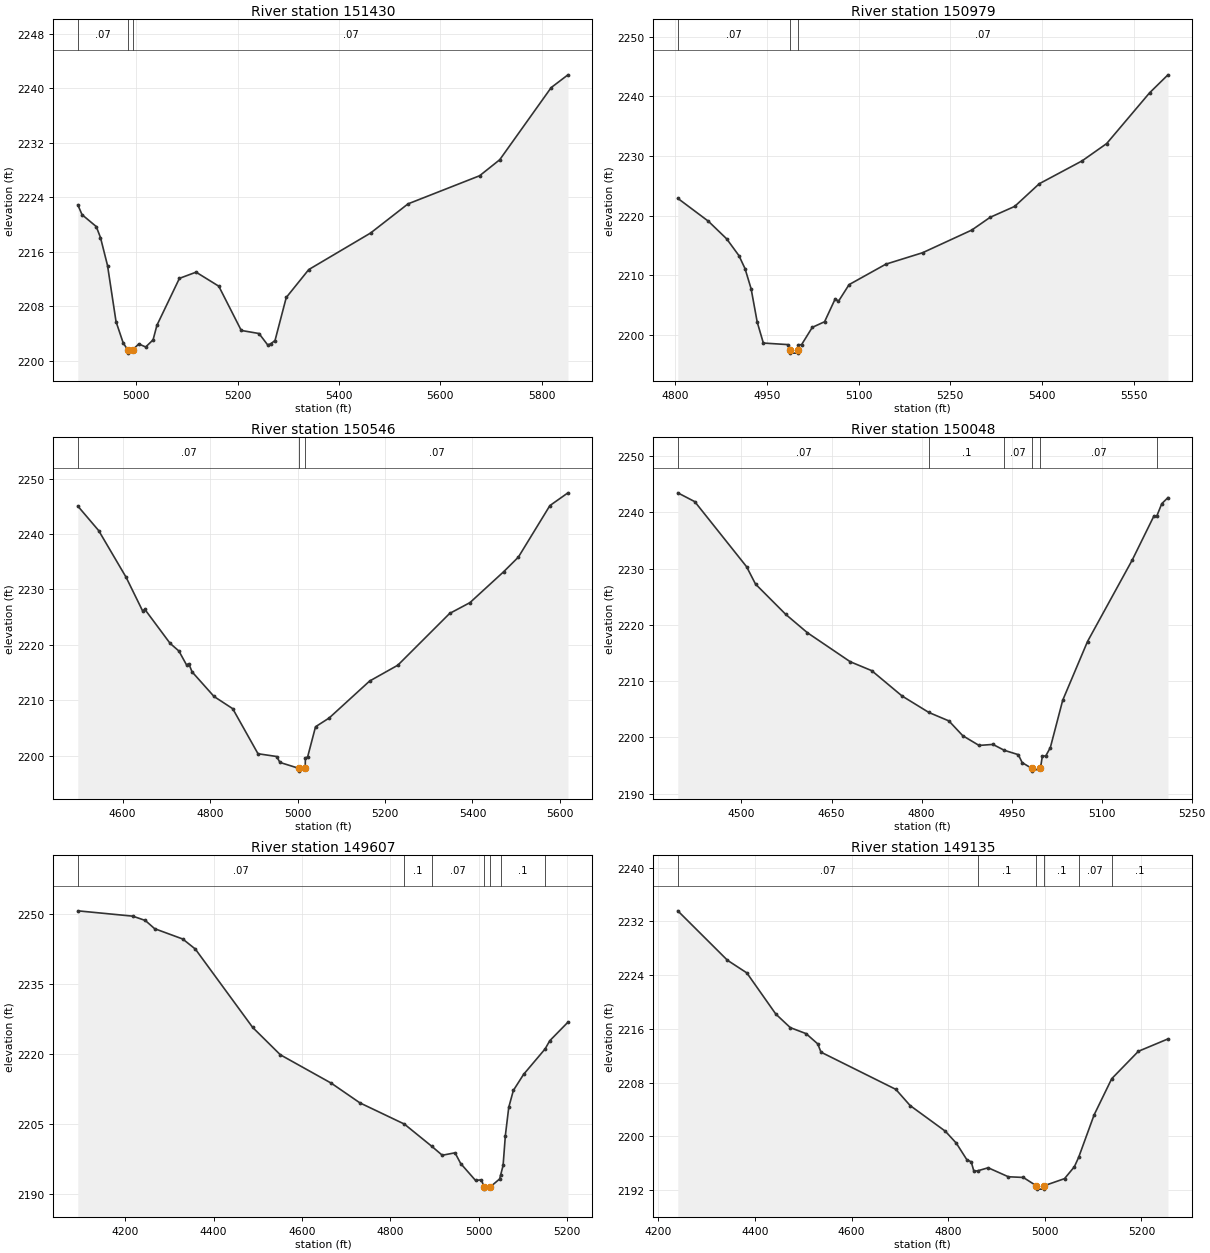
Type RM Length L Ch R = 1 ,151430  ,451,451,451
BEGIN DESCRIPTION:
South Fork Guadalupe River 244.0
END DESCRIPTION:
XS GIS Cut Line= 3
      1788574.98     13892175.03        1788625.       13892075.
      1788996.17     13891303.93
#Sta/Elev= 30
  4884.3 2222.91  4892.7 2221.46  4920.7 2219.72  4929.1  2218.1    4943 2213.99
  4959.8 2205.75  4973.8 2202.65  4982.6 2201.63  4983.1 2201.13  4992.9 2201.63
  5004.7 2202.48  5018.3 2202.03  5032.9 2203.08  5040.5 2205.22  5084.9 2212.11
  5117.8 2213.02  5162.6 2210.96    5207 2204.46    5242 2204.01  5259.1 2202.34
  5264.7 2202.48  5273.6 2202.98  5295.8  2209.3  5340.2  2213.4  5462.3 2218.77
  5536.2 2223.05  5677.5 2227.18  5717.2 2229.53  5818.8 2240.13  5851.9    2242
#Mann= 3 ,-1 , 0
  4884.3     .07       0  4982.6     .05       0  4992.9     .07       0
Bank Sta=4982.6,4992.9
XS Rating Curve= 0 ,0
Exp/Cntr=0.3,0.1

Type RM Length L Ch R = 1 ,150979  ,433,433,433
BEGIN DESCRIPTION:
South Fork Guadalupe River 243.0
END DESCRIPTION:
XS GIS Cut Line= 3
        1789025.     13892125.04        1789025.       13891925.
        1789075.     13891325.02
#Sta/Elev= 30
    4804 2222.89    4854 2219.06    4884  2216.1    4904  2213.3    4914 2211.12
    4924 2207.73    4934 2202.14    4944 2198.64    4984 2198.38  4986.9 2197.45
  4987.4 2196.95  5000.6 2196.95  5001.1 2197.45  5001.5 2198.36  5006.5 2198.36
  5024.1 2201.27  5044.2 2202.21  5061.7 2206.07  5066.8 2205.62  5084.3 2208.43
  5144.5 2211.86  5204.7 2213.78    5285 2217.57  5315.1 2219.71  5355.3 2221.54
  5395.4 2225.33  5465.6 2229.17  5505.8 2232.07    5576 2240.57  5606.1 2243.59
#Mann= 3 ,-1 , 0
    4804     .07       0  4986.9     .05       0  5001.1     .07       0
Bank Sta=4986.9,5001.1
XS Rating Curve= 0 ,0
Exp/Cntr=0.3,0.1

Type RM Length L Ch R = 1 ,150546  ,498,498,498
BEGIN DESCRIPTION:
South Fork Guadalupe River 242.0
END DESCRIPTION:
XS GIS Cut Line= 3
        1789475.     13892325.01        1789425.       13891825.
      1789274.99     13891224.97
#Sta/Elev= 30
  4497.4 2245.04  4545.1 2240.62    4608 2232.17  4645.6 2226.12  4650.7  2226.4
  4708.5 2220.26  4728.6 2218.88  4746.1 2216.37  4751.2 2216.59  4758.7 2215.12
    4809 2210.67  4851.7 2208.47  4909.5 2200.34  4952.2 2199.84  4959.7 2198.77
  5003.1  2197.7  5003.6  2197.2  5017.4  2197.7  5017.9 2199.54  5023.1 2199.79
  5041.1 2205.21  5072.1 2206.78  5164.8 2213.46  5229.3 2216.32  5347.8 2225.66
  5394.2 2227.61  5471.5  2233.2    5505 2235.83  5577.1 2245.13  5618.4 2247.43
#Mann= 3 ,-1 , 0
  4497.4     .07       0  5003.1     .05       0  5017.4     .07       0
Bank Sta=5003.1,5017.4
XS Rating Curve= 0 ,0
Exp/Cntr=0.3,0.1

Type RM Length L Ch R = 1 ,150048  ,441,441,441
BEGIN DESCRIPTION:
South Fork Guadalupe River 241.0
END DESCRIPTION:
XS GIS Cut Line= 3
      1789575.01     13892324.99        1789925.       13891825.
      1789975.01     13891624.97
#Sta/Elev= 30
  4393.9 2243.49  4422.2 2241.92  4508.5 2230.35  4523.4 2227.26  4573.9 2221.86
  4609.7 2218.62  4681.2 2213.45  4716.9 2211.87  4767.5 2207.36  4812.2 2204.43
  4845.5 2202.93  4868.6  2200.3  4895.7 2198.57  4918.8 2198.75  4937.9  2197.7
  4961.1 2196.93  4967.6 2195.51  4983.4  2194.5  4983.9    2194    4998  2194.5
  5001.2 2196.69  5006.8 2196.69  5014.5  2198.2  5035.1 2206.61  5076.4 2217.05
  5151.1 2231.58  5187.2 2239.41  5191.8 2239.36  5200.1 2241.56  5210.4 2242.64
#Mann= 6 ,-1 , 0
  4393.9     .07       0  4812.2      .1       0  4937.9     .07       0
  4983.4     .05       0    4998     .07       0  5191.8    .035       0
Bank Sta=4983.4,4998
XS Rating Curve= 0 ,0
Exp/Cntr=0.3,0.1

Type RM Length L Ch R = 1 ,149607  ,472,472,472
BEGIN DESCRIPTION:
South Fork Guadalupe River 240.0
END DESCRIPTION:
XS GIS Cut Line= 4
      1789570.02     13892635.92      1789741.75     13892462.82
        1790275.       13892075.      1790324.99     13891875.05
#Sta/Elev= 30
  4092.6 2250.62    4217 2249.48  4245.3 2248.56  4266.5  2246.8  4330.1 2244.59
  4358.6 2242.44  4488.4 2225.67    4551 2219.82  4666.2 2213.75  4731.1 2209.53
  4831.6    2205  4893.2 2200.28  4917.4 2198.33  4946.3 2198.85  4959.1 2196.56
  4992.7 2192.94  5006.1 2193.07  5011.7 2191.58  5012.2 2191.08  5026.3 2191.58
  5047.3 2193.26  5049.7 2194.15  5055.1 2196.15  5060.2 2202.52  5067.9 2208.57
  5078.3 2212.19  5101.4 2215.62  5150.2 2221.08  5160.7 2222.83  5201.9  2226.8
#Mann= 7 ,-1 , 0
  4092.6     .07       0  4831.6      .1       0  4893.2     .07       0
  5011.7     .05       0  5026.3     .07       0  5049.7      .1       0
  5150.2     .07       0
Bank Sta=5011.7,5026.3
XS Rating Curve= 0 ,0
Exp/Cntr=0.3,0.1

Type RM Length L Ch R = 1 ,149135  ,554,554,554
BEGIN DESCRIPTION:
South Fork Guadalupe River 239.0
END DESCRIPTION:
XS GIS Cut Line= 4
      1790444.99     13893097.75      1790434.88      13892850.3
        1790625.       13892375.        1790675.     13892125.02
#Sta/Elev= 30
  4240.4 2233.56  4343.2  2226.2  4383.3 2224.32  4443.3 2218.19  4473.3 2216.17
  4505.9 2215.28  4530.1 2213.75  4536.8 2212.52  4691.7 2206.98  4721.3 2204.57
    4794 2200.76  4816.9 2198.97  4838.4 2196.54  4847.8 2196.18  4853.2  2194.8
  4861.3 2194.86  4882.8 2195.31  4924.6 2193.97  4955.5 2193.87  4982.5 2192.63
    4983 2192.13    4998 2192.13  4998.5 2192.63  5040.8 2193.69  5061.2 2195.46
  5070.1 2196.87    5102 2203.17  5138.5 2208.57  5193.7 2212.65  5254.9 2214.49
#Mann= 6 ,-1 , 0
  4240.4     .07       0  4861.3      .1       0  4982.5     .05       0
  4998.5      .1       0  5070.1     .07       0  5138.5      .1       0
Bank Sta=4982.5,4998.5
XS Rating Curve= 0 ,0
Exp/Cntr=0.3,0.1

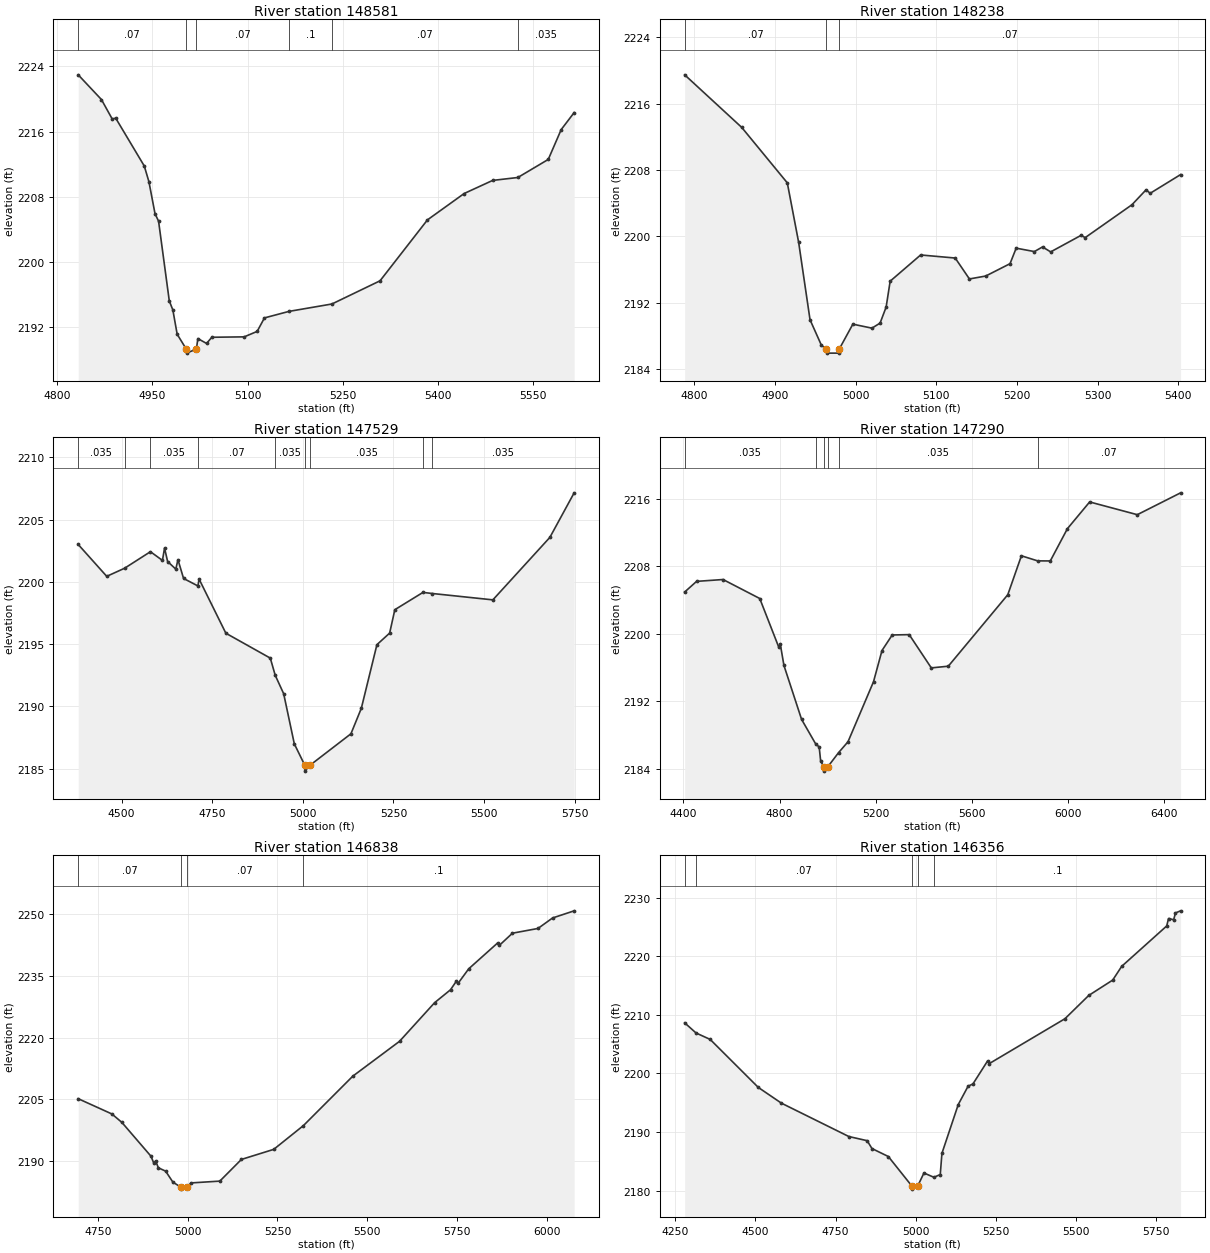
Type RM Length L Ch R = 1 ,148581  ,343,343,343
BEGIN DESCRIPTION:
South Fork Guadalupe River 238.0
END DESCRIPTION:
XS GIS Cut Line= 3
      1790724.99     13892925.03      1790812.49      13892746.3
      1790925.01     13892174.97
#Sta/Elev= 30
  4833.2 2222.97  4869.8 2219.93  4886.7 2217.55  4892.3 2217.64  4937.3 2211.76
  4944.6 2209.83  4954.2  2205.9  4959.8 2204.98  4976.7 2195.17  4982.3 2194.07
  4989.1 2191.08  5003.4 2189.26  5003.9 2188.76  5019.4 2189.26  5021.7 2190.55
  5035.4 2189.95  5043.7 2190.71  5094.7 2190.76  5115.1 2191.43  5126.6 2193.09
  5165.2 2193.89  5232.9  2194.8  5308.7 2197.65  5383.4 2205.14  5441.2 2208.38
  5486.1 2209.99  5525.8 2210.35  5573.7 2212.57  5594.1 2216.24  5614.5 2218.33
#Mann= 6 ,-1 , 0
  4833.2     .07       0  5003.4     .05       0  5019.4     .07       0
  5165.2      .1       0  5232.9     .07       0  5525.8    .035       0
Bank Sta=5003.4,5019.4
XS Rating Curve= 0 ,0
Exp/Cntr=0.3,0.1

Type RM Length L Ch R = 1 ,148238  ,709,709,709
BEGIN DESCRIPTION:
South Fork Guadalupe River 237.0
END DESCRIPTION:
XS GIS Cut Line= 3
      1790975.01     13892974.99        1791125.       13892825.
        1791175.     13892425.03
#Sta/Elev= 30
  4787.9 2219.47  4858.6 2213.14  4915.2 2206.45  4929.3 2199.27  4943.4 2189.95
  4957.6 2186.86  4963.7 2186.43  4964.2 2185.93  4979.2 2185.93  4979.7 2186.43
  4996.5 2189.42  5020.2 2188.94  5030.3 2189.55  5037.8 2191.48  5042.8  2194.6
  5080.6 2197.76  5123.5 2197.39  5141.1 2194.87  5161.3 2195.22  5191.5 2196.71
  5199.1 2198.58  5221.7 2198.17  5231.8 2198.73  5241.9 2198.13  5279.7 2200.13
  5284.7 2199.85  5342.7 2203.81  5360.3 2205.62  5365.3 2205.19  5403.1 2207.45
#Mann= 3 ,-1 , 0
  4787.9     .07       0  4963.7     .05       0  4979.7     .07       0
Bank Sta=4963.7,4979.7
XS Rating Curve= 0 ,0
Exp/Cntr=0.3,0.1

Type RM Length L Ch R = 1 ,147529  ,239,239,239
BEGIN DESCRIPTION:
South Fork Guadalupe River 236.0
END DESCRIPTION:
XS GIS Cut Line= 4
      1792120.87     13893456.76      1791804.67     13892928.03
      1791587.61     13892666.83      1791262.99     13892411.96
#Sta/Elev= 30
  4380.1 2203.01  4458.8 2200.45    4508  2201.1  4579.4 2202.43  4612.5 2201.73
  4618.3 2202.72  4626.8 2201.64  4649.4 2201.03  4655.3 2201.79  4670.8 2200.28
  4710.3 2199.68  4713.6 2200.23  4787.5 2195.88  4910.1 2193.88  4923.7  2192.5
    4947 2191.02  4976.4 2186.99  5004.8  2185.3  5005.3  2184.8  5020.9  2185.3
  5132.6  2187.8  5161.3 2189.85  5204.3 2194.96  5239.4 2195.89  5253.7 2197.77
  5331.4 2199.16  5357.6 2199.07  5524.2 2198.56  5681.5 2203.58  5748.5 2207.16
#Mann= 9 ,-1 , 0
  4380.1    .035       0    4508      .1       0  4579.4    .035       0
  4710.3     .07       0  4923.7    .035       0  5004.8    .035       0
  5020.9    .035       0  5331.4     .07       0  5357.6    .035       0
Bank Sta=5004.8,5020.9
XS Rating Curve= 0 ,0
Exp/Cntr=0.3,0.1

Type RM Length L Ch R = 1 ,147290  ,452,452,452
BEGIN DESCRIPTION:
South Fork Guadalupe River 235.0
END DESCRIPTION:
XS GIS Cut Line= 4
      1792336.25     13893381.61        1792025.       13892875.
      1791364.66     13892207.95      1790954.26     13891872.89
#Sta/Elev= 30
  4405.5 2204.96    4455 2206.22  4565.1 2206.44  4717.8 2204.19  4797.1 2198.41
    4803 2198.82  4818.4 2196.26  4891.8 2189.87  4951.5 2186.91  4964.9 2186.62
  4971.1 2184.95  4984.3 2184.24  4984.8 2183.74  5000.5 2184.24  5045.4 2185.92
  5084.9 2187.22    5191 2194.33  5226.3 2198.03  5268.8 2199.87  5339.5 2199.91
  5431.4 2195.97  5502.1 2196.17  5749.6 2204.64  5806.2 2209.25  5873.6 2208.65
  5926.4 2208.64  5997.5 2212.46  6090.1 2215.63  6288.3 2214.12  6468.5 2216.71
#Mann= 6 ,-1 , 0
  4405.5    .035       0  4951.5     .07       0  4984.3     .05       0
  5000.5     .07       0  5045.4    .035       0  5873.6     .07       0
Bank Sta=4984.3,5000.5
XS Rating Curve= 0 ,0
Exp/Cntr=0.3,0.1

Type RM Length L Ch R = 1 ,146838  ,482,482,482
BEGIN DESCRIPTION:
South Fork Guadalupe River 234.0
END DESCRIPTION:
XS GIS Cut Line= 4
      1792375.01     13893124.95        1792425.       13892825.
        1792425.       13892225.      1792344.93     13891755.77
#Sta/Elev= 30
  4695.6 2205.13  4789.3 2201.42  4817.2 2199.36  4898.3 2191.12  4905.9 2189.46
    4911 2190.02  4918.6 2188.33  4938.9 2187.51  4959.1 2184.84  4980.8 2183.64
  4981.3 2183.14  4998.3 2183.64  5009.7 2184.65  5089.7 2185.09  5149.7 2190.36
  5239.7 2192.81  5322.4  2198.6  5459.7 2210.61  5589.7 2219.08  5687.4 2228.48
  5731.6 2231.62  5747.6 2233.67  5752.6 2233.18  5782.3 2236.72  5862.8 2243.01
  5867.9 2242.45    5904 2245.38    5975 2246.53  6015.6 2249.08  6075.7 2250.82
#Mann= 4 ,-1 , 0
  4695.6     .07       0  4980.8     .05       0  4998.3     .07       0
  5322.4      .1       0
Bank Sta=4980.8,4998.3
XS Rating Curve= 0 ,0
Exp/Cntr=0.3,0.1

Type RM Length L Ch R = 1 ,146356  ,453,453,453
BEGIN DESCRIPTION:
South Fork Guadalupe River 233.0
END DESCRIPTION:
XS GIS Cut Line= 4
      1792475.01     13893324.99        1792875.       13892725.
      1792795.47     13892327.72      1792590.01     13891959.98
#Sta/Elev= 30
  4279.3 2208.64  4314.7 2206.91  4358.9 2205.81  4509.1 2197.62  4581.2 2194.94
  4791.6 2189.25  4848.7 2188.54  4863.7  2187.2  4914.8 2185.84  4988.6 2180.78
  4989.1 2180.28  5006.2 2180.78  5025.9 2183.03    5057  2182.3  5076.8 2182.77
    5082 2186.38    5133 2194.71  5163.6 2197.83  5178.8 2198.22  5224.7 2202.16
  5229.8 2201.69  5465.9 2209.34  5540.1 2213.31  5614.9 2215.93  5642.9 2218.27
  5783.4 2225.16  5789.1 2226.43  5805.1 2226.22  5810.8 2227.38  5826.8 2227.74
#Mann= 5 ,-1 , 0
  4279.3      .1       0  4314.7     .07       0  4988.6     .05       0
  5006.2     .07       0    5057      .1       0
Bank Sta=4988.6,5006.2
XS Rating Curve= 0 ,0
Exp/Cntr=0.3,0.1

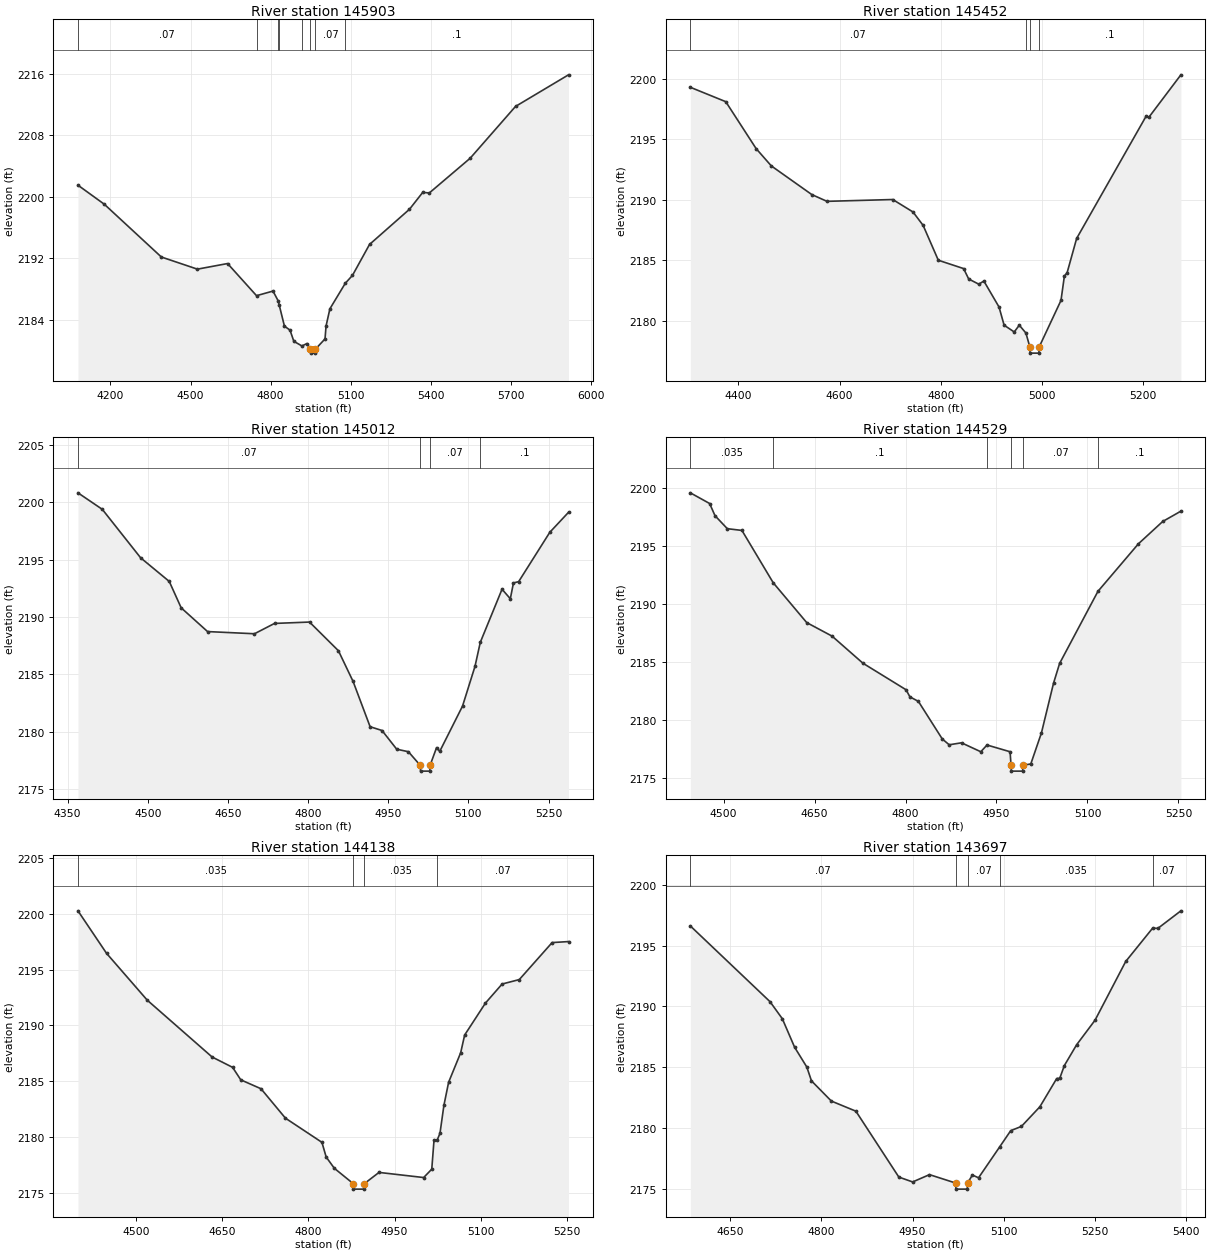
Type RM Length L Ch R = 1 ,145903  ,451,451,451
BEGIN DESCRIPTION:
South Fork Guadalupe River 232.0
END DESCRIPTION:
XS GIS Cut Line= 4
        1792675.       13893375.        1793275.       13892675.
        1793525.       13892375.      1793869.96     13891979.98
#Sta/Elev= 30
  4078.4 2201.49  4177.2 2199.01  4390.7 2192.15  4525.7 2190.57  4638.7  2191.3
  4747.1 2187.12  4808.8 2187.72  4828.1 2186.45  4831.6 2185.97  4851.6 2183.16
  4872.5 2182.64  4886.8 2181.19  4917.1 2180.58  4936.1  2180.9    4949 2180.15
  4949.5 2179.65  4966.7 2179.65  4967.2 2180.15  5003.6  2181.5  5007.5 2183.18
  5021.8 2185.41  5079.6 2188.74  5106.4 2189.76  5170.2 2193.78  5319.9 2198.36
  5369.4 2200.55  5394.2 2200.48    5547 2204.99  5716.9 2211.73  5915.3 2215.84
#Mann= 8 ,-1 , 0
  4078.4     .07       0  4747.1      .1       0  4828.1     .07       0
  4831.6      .1       0  4917.1     .07       0    4949     .05       0
  4967.2     .07       0  5079.6      .1       0
Bank Sta=4949,4967.2
XS Rating Curve= 0 ,0
Exp/Cntr=0.3,0.1

Type RM Length L Ch R = 1 ,145452  ,440,440,440
BEGIN DESCRIPTION:
South Fork Guadalupe River 231.0
END DESCRIPTION:
XS GIS Cut Line= 3
        1793675.     13893525.04        1793675.       13892825.
        1793775.       13892575.
#Sta/Elev= 30
    4305 2199.29    4375  2198.1    4435 2194.22    4465 2192.79    4545 2190.42
    4575 2189.86    4705 2190.01    4745 2188.98    4765 2187.87    4795 2184.99
    4845  2184.3    4855 2183.44    4875 2183.01    4885 2183.27    4915 2181.12
    4925 2179.62    4945 2179.06    4955 2179.62  4968.1 2178.97  4975.9 2177.81
  4976.4 2177.31  4993.7 2177.31  4994.2 2177.81  5037.4 2181.67  5044.1 2183.68
  5049.5 2183.96  5068.3 2186.79  5205.6  2196.9    5211 2196.81  5274.3 2200.32
#Mann= 4 ,-1 , 0
    4305     .07       0  4968.1      .1       0  4975.9     .05       0
  4994.2      .1       0
Bank Sta=4975.9,4994.2
XS Rating Curve= 0 ,0
Exp/Cntr=0.3,0.1

Type RM Length L Ch R = 1 ,145012  ,483,483,483
BEGIN DESCRIPTION:
South Fork Guadalupe River 230.0
END DESCRIPTION:
XS GIS Cut Line= 3
      1793724.99     13893575.02        1794025.       13893025.
      1794175.02     13892774.97
#Sta/Elev= 30
  4369.3 2200.82  4414.9 2199.38  4486.6 2195.16  4540.2  2193.1  4562.5  2190.8
  4611.9 2188.73  4699.7 2188.54  4737.2 2189.44  4802.7 2189.56  4856.8 2187.06
  4884.3 2184.38  4916.1 2180.44  4938.4 2180.11  4965.9 2178.48  4987.8 2178.26
    5010 2177.07  5010.5 2176.57  5027.8 2176.57  5028.3 2177.07  5040.5 2178.62
  5046.4 2178.29  5089.1 2182.24  5112.4  2185.7  5122.3 2187.79    5163 2192.42
  5178.5 2191.59  5184.4 2192.97  5194.1 2193.08  5252.4 2197.38  5287.4 2199.12
#Mann= 4 ,-1 , 0
  4369.3     .07       0    5010     .05       0  5028.3     .07       0
  5122.3      .1       0
Bank Sta=5010,5028.3
XS Rating Curve= 0 ,0
Exp/Cntr=0.3,0.1

Type RM Length L Ch R = 1 ,144529  ,391,391,391
BEGIN DESCRIPTION:
South Fork Guadalupe River 229.0
END DESCRIPTION:
XS GIS Cut Line= 3
        1794375.     13893675.02        1794475.       13893125.
        1794475.     13892875.03
#Sta/Elev= 30
  4445.1 2199.55  4476.9 2198.63  4485.8 2197.58  4506.1 2196.46  4530.2 2196.31
  4581.8  2191.8    4637 2188.37  4678.9  2187.2  4729.7 2184.87  4800.9 2182.58
  4807.2 2181.97  4821.2 2181.58  4860.6 2178.34    4872 2177.84  4892.3 2178.01
  4924.1 2177.24  4934.4 2177.82  4972.4 2177.24    4974 2176.07  4974.5 2175.57
  4993.1 2175.57  4993.6 2176.07  5006.6 2176.19  5024.1 2178.86  5044.1 2183.15
  5054.1 2184.85  5117.3 2191.06  5184.1 2195.16  5224.1 2197.08  5254.1 2197.97
#Mann= 6 ,-1 , 0
  4445.1    .035       0  4581.8      .1       0  4934.4     .07       0
    4974     .05       0  4993.6     .07       0  5117.3      .1       0
Bank Sta=4974,4993.6
XS Rating Curve= 0 ,0
Exp/Cntr=0.3,0.1

Type RM Length L Ch R = 1 ,144138  ,441,441,441
BEGIN DESCRIPTION:
South Fork Guadalupe River 228.0
END DESCRIPTION:
XS GIS Cut Line= 3
      1794424.98     13893675.02      1794845.21     13893218.43
      1794975.01     13893024.98
#Sta/Elev= 30
  4399.1 2200.29  4448.8 2196.48  4519.7 2192.27  4632.5 2187.17  4668.2 2186.24
  4682.4 2185.12  4717.6 2184.32  4760.1 2181.68  4823.6 2179.51    4831 2178.19
  4845.2 2177.18  4877.9 2175.81  4878.4 2175.31  4897.1 2175.31  4897.6 2175.81
  4922.9 2176.81  5000.6 2176.35  5014.7  2177.1  5018.6 2179.69  5024.1 2179.71
    5029 2180.32  5035.8 2182.82    5044  2184.9    5065 2187.55  5071.9 2189.14
  5108.1 2192.01  5137.1 2193.72    5167 2194.12  5224.1 2197.44  5252.6 2197.53
#Mann= 4 ,-1 , 0
  4399.1    .035       0  4877.9    .035       0  4897.6    .035       0
  5024.1     .07       0
Bank Sta=4877.9,4897.6
XS Rating Curve= 0 ,0
Exp/Cntr=0.3,0.1

Type RM Length L Ch R = 1 ,143697  ,494,494,494
BEGIN DESCRIPTION:
South Fork Guadalupe River 227.0
END DESCRIPTION:
XS GIS Cut Line= 3
        1795025.     13893825.04        1795075.       13893425.
        1795125.     13893024.96
#Sta/Elev= 30
  4584.7 2196.61  4715.7 2190.39  4735.9 2188.99  4756.1 2186.65  4776.2 2185.02
  4783.8 2183.89  4816.5 2182.23  4856.8  2181.4  4927.4 2175.99  4950.1 2175.59
  4977.8 2176.19  5020.8  2175.5  5021.3    2175    5040    2175  5040.5  2175.5
  5048.3 2176.16  5058.4 2175.93  5092.9 2178.45  5111.3  2179.8  5128.9 2180.15
  5159.2 2181.76  5186.9 2184.08  5191.9  2184.1  5199.5 2185.15  5219.6 2186.85
  5249.9 2188.87  5300.3 2193.69  5344.6 2196.43  5353.2 2196.41    5391 2197.85
#Mann= 5 ,-1 , 0
  4584.7     .07       0  5020.8     .05       0  5040.5     .07       0
  5092.9    .035       0  5344.6     .07       0
Bank Sta=5020.8,5040.5
XS Rating Curve= 0 ,0
Exp/Cntr=0.3,0.1

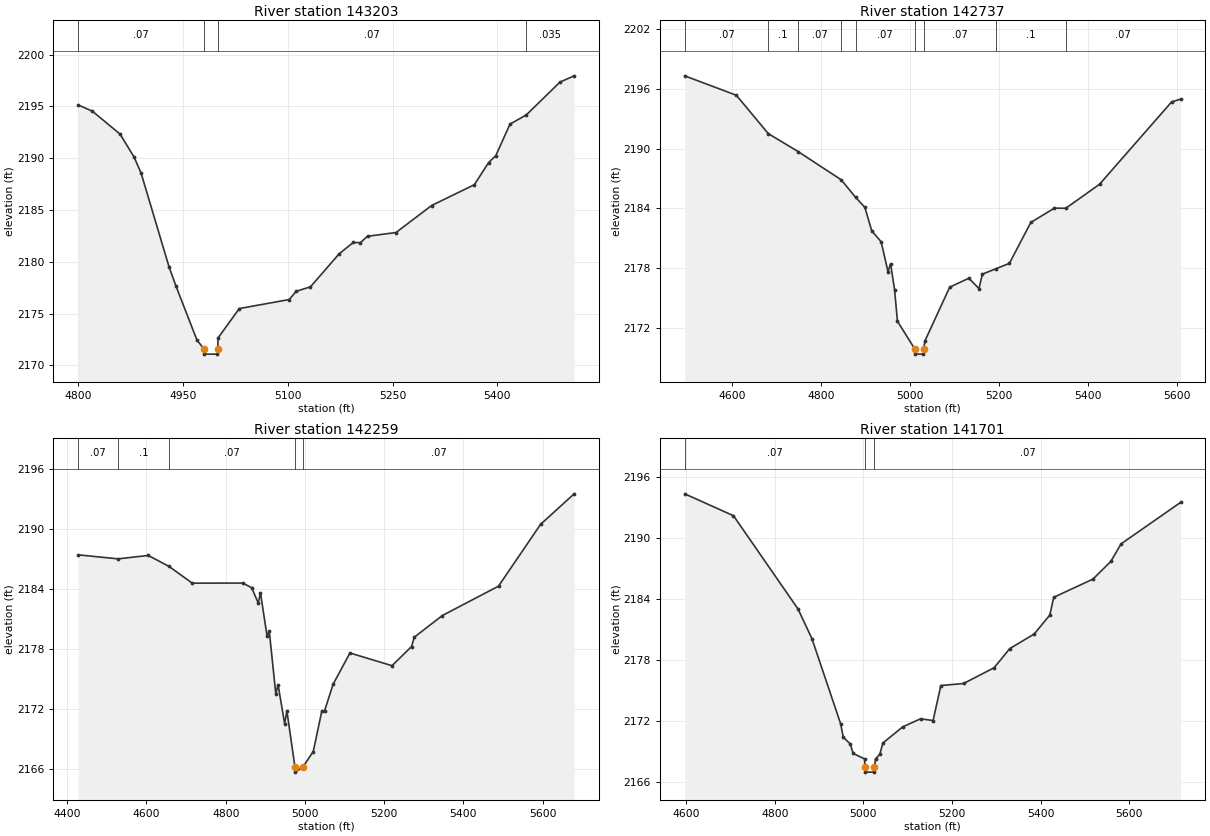
Type RM Length L Ch R = 1 ,143203  ,466,466,466
BEGIN DESCRIPTION:
South Fork Guadalupe River 226.0
END DESCRIPTION:
XS GIS Cut Line= 3
        1795525.     13893724.98        1795525.       13893525.
        1795425.     13893024.98
#Sta/Elev= 30
    4800 2195.13    4820 2194.55    4860 2192.32    4880  2190.1    4890 2188.56
    4930 2179.51    4940 2177.64    4970 2172.43  4980.1 2171.58  4980.6 2171.08
  4999.3 2171.08  4999.8 2171.58    5000 2172.63  5030.6 2175.48    5102 2176.35
  5112.2 2177.15  5132.5 2177.58  5173.3 2180.75  5193.7 2181.86  5203.9 2181.84
  5214.1 2182.46  5254.9 2182.82  5305.9 2185.43  5367.1 2187.44  5387.5 2189.58
  5397.7 2190.24  5418.1 2193.29  5441.5 2194.18  5489.5 2197.34  5509.9 2197.95
#Mann= 4 ,-1 , 0
    4800     .07       0  4980.1     .05       0  4999.8     .07       0
  5441.5    .035       0
Bank Sta=4980.1,4999.8
XS Rating Curve= 0 ,0
Exp/Cntr=0.3,0.1

Type RM Length L Ch R = 1 ,142737  ,478,478,478
BEGIN DESCRIPTION:
South Fork Guadalupe River 225.0
END DESCRIPTION:
XS GIS Cut Line= 3
      1795707.14     13894006.16        1795975.       13893575.
      1795874.99     13892974.97
#Sta/Elev= 30
  4492.5 2197.31  4608.7 2195.36  4680.6 2191.51  4747.6 2189.71  4844.8 2186.87
  4876.9 2185.12  4897.9 2184.11  4913.3 2181.76  4934.6 2180.65  4949.9 2177.66
  4955.8 2178.44  4964.8 2175.84  4971.2 2172.68  5010.5 2169.87    5011 2169.37
  5029.7 2169.37  5030.2 2169.87    5033 2170.69  5088.8 2176.09  5131.9 2176.99
  5154.7 2175.95  5162.3  2177.4  5192.1 2177.93  5223.1 2178.48  5271.3 2182.59
  5324.5 2184.03  5349.9 2184.01  5425.9 2186.42  5588.1 2194.69  5608.4 2194.97
#Mann= 9 ,-1 , 0
  4492.5     .07       0  4680.6      .1       0  4747.6     .07       0
  4844.8      .1       0  4876.9     .07       0  5010.5     .05       0
  5030.2     .07       0  5192.1      .1       0  5349.9     .07       0
Bank Sta=5010.5,5030.2
XS Rating Curve= 0 ,0
Exp/Cntr=0.3,0.1

Type RM Length L Ch R = 1 ,142259  ,558,558,558
BEGIN DESCRIPTION:
South Fork Guadalupe River 224.0
END DESCRIPTION:
XS GIS Cut Line= 3
      1796161.45     13893991.24        1796425.       13893475.
        1795975.       13892975.
#Sta/Elev= 30
  4427.6 2187.37  4528.4 2186.97  4604.5 2187.31  4657.1 2186.21  4715.6 2184.54
  4843.3 2184.55  4865.6 2184.08  4882.2 2182.56  4887.8 2183.59  4904.4 2179.25
    4910 2179.77  4926.6 2173.45  4932.2  2174.4  4948.9 2170.49  4954.5 2171.78
  4974.9 2166.15  4975.4 2165.65  4994.7 2166.15  5021.1 2167.71  5042.7 2171.75
  5049.5 2171.75  5071.1 2174.42  5113.7 2177.56  5219.9 2176.29  5269.2  2178.2
  5276.3 2179.14  5346.9  2181.3  5488.9 2184.24  5595.1 2190.42  5679.9 2193.47
#Mann= 5 ,-1 , 0
  4427.6     .07       0  4528.4      .1       0  4657.1     .07       0
  4974.9     .05       0  4994.7     .07       0
Bank Sta=4974.9,4994.7
XS Rating Curve= 0 ,0
Exp/Cntr=0.3,0.1

Type RM Length L Ch R = 1 ,141701  ,565,565,565
BEGIN DESCRIPTION:
South Fork Guadalupe River 223.0
END DESCRIPTION:
XS GIS Cut Line= 3
      1797125.01     13893675.01        1796925.       13893325.
      1796625.01     13892675.01
#Sta/Elev= 30
  4596.8 2194.32  4706.9 2192.17  4852.4 2183.01    4884 2180.08  4948.8 2171.71
  4954.6  2170.4  4970.4 2169.74  4976.9 2168.81  5002.7 2168.27  5003.4 2167.47
  5003.9 2166.97  5024.4 2166.97  5024.9 2167.47  5027.5 2168.28  5037.1 2168.72
    5044 2169.83  5088.5 2171.41  5128.9 2172.21  5157.3 2172.04  5174.8 2175.48
  5226.2 2175.68    5295 2177.23  5330.3 2179.11  5385.4 2180.54  5420.7 2182.41
  5429.5 2184.15    5518 2185.94  5558.4 2187.68  5581.4  2189.4  5715.8 2193.48
#Mann= 3 ,-1 , 0
  4596.8     .07       0  5003.4     .05       0  5024.9     .07       0
Bank Sta=5003.4,5024.9
XS Rating Curve= 0 ,0
Exp/Cntr=0.3,0.1