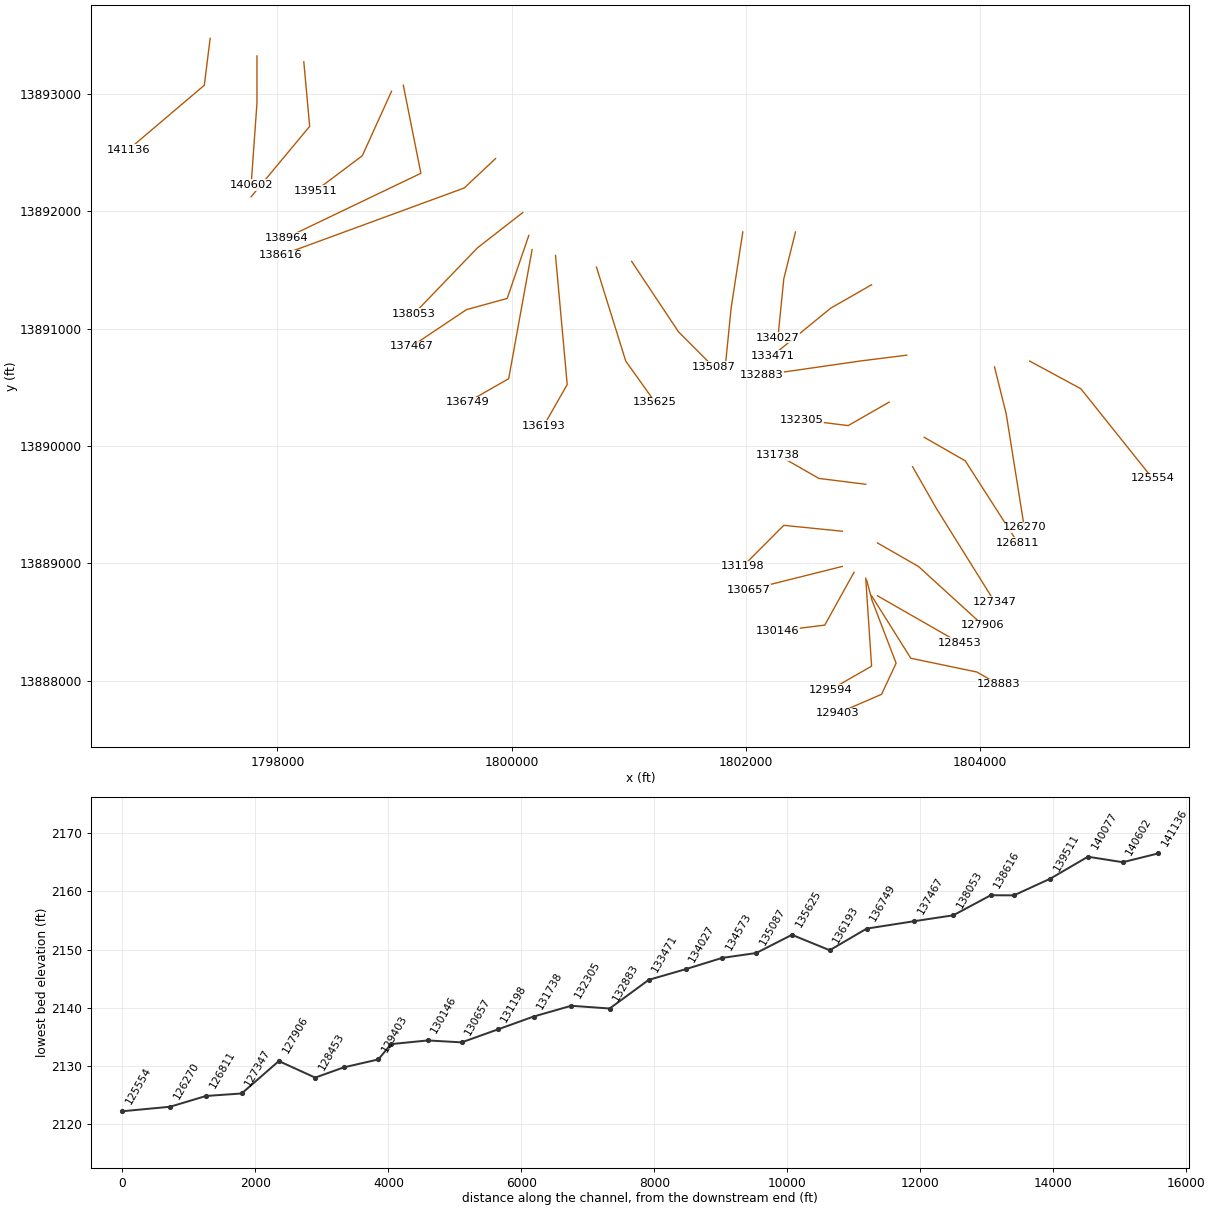
HEC-RAS study South Fork Guadalupe River.prj: South Fork Guadalupe River Base Level Engineering

--- South Fork Guadalupe River.g01 (geometry) --- (continued)

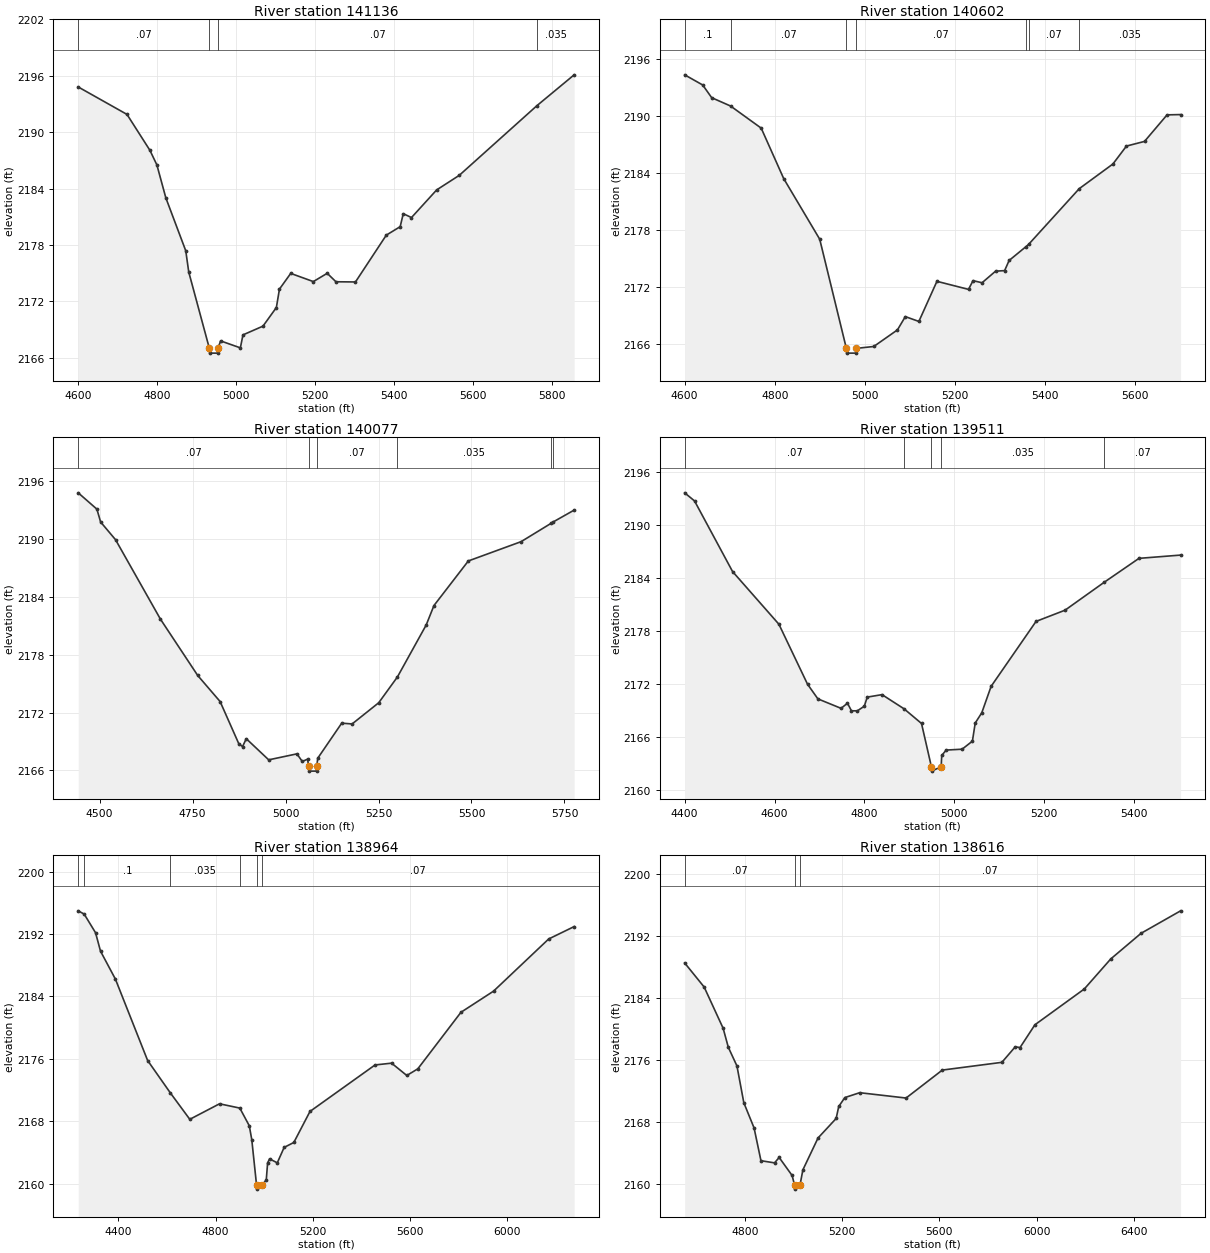
Type RM Length L Ch R = 1 ,141136  ,534,534,534
BEGIN DESCRIPTION:
South Fork Guadalupe River 222.0
END DESCRIPTION:
XS GIS Cut Line= 3
        1797425.     13893474.97        1797375.       13893075.
      1796724.96     13892524.97
#Sta/Elev= 30
  4601.3 2194.81  4724.7 2191.89  4782.7 2188.07  4800.3 2186.52    4823 2183.01
  4873.4 2177.38  4880.9 2175.13  4933.1    2167  4933.6  2166.5  4954.2  2166.5
  4954.7    2167  4961.6  2167.8  5011.5 2167.06  5018.1 2168.44  5068.7 2169.37
  5102.6 2171.35  5110.4 2173.31  5138.9 2174.98  5196.1 2174.11  5231.2 2174.99
  5253.3 2174.09  5302.7 2174.07  5380.7 2179.05  5415.8 2179.95  5423.6 2181.33
  5444.4 2180.92  5508.1 2183.86  5565.3 2185.41    5762 2192.83  5855.9  2196.1
#Mann= 4 ,-1 , 0
  4601.3     .07       0  4933.1     .05       0  4954.7     .07       0
    5762    .035       0
Bank Sta=4933.1,4954.7
XS Rating Curve= 0 ,0
Exp/Cntr=0.3,0.1

Type RM Length L Ch R = 1 ,140602  ,525,525,525
BEGIN DESCRIPTION:
South Fork Guadalupe River 221.0
END DESCRIPTION:
XS GIS Cut Line= 3
        1797825.       13893325.        1797825.       13892925.
        1797775.     13892224.98
#Sta/Elev= 30
    4600 2194.33    4640 2193.26    4660 2191.92    4702 2191.04    4770 2188.71
    4820 2183.39    4900    2177  4959.2 2165.49  4959.7 2164.99  4980.4 2164.99
  4980.9 2165.49  5020.1 2165.69  5072.7 2167.44  5090.2 2168.84  5120.3 2168.33
  5160.4 2172.56  5230.6 2171.71  5240.6 2172.63  5260.7 2172.41  5290.7 2173.63
  5310.8 2173.69  5320.8 2174.76  5358.6 2176.23    5364 2176.45  5476.6 2182.33
  5551.4 2184.93  5581.5 2186.82  5621.6 2187.31  5671.7 2190.11  5701.8 2190.14
#Mann= 7 ,-1 , 0
    4600      .1       0    4702     .07       0  4959.2     .05       0
  4980.9     .07       0  5358.6      .1       0    5364     .07       0
  5476.6    .035       0
Bank Sta=4959.2,4980.9
XS Rating Curve= 0 ,0
Exp/Cntr=0.3,0.1

Type RM Length L Ch R = 1 ,140077  ,566,566,566
BEGIN DESCRIPTION:
South Fork Guadalupe River 220.0
END DESCRIPTION:
XS GIS Cut Line= 3
        1798225.     13893274.98        1798275.       13892725.
      1797774.98     13892124.98
#Sta/Elev= 30
  4442.7 2194.77  4492.9 2193.08  4502.9 2191.75  4543.1 2189.91  4663.6 2181.69
    4764 2175.84  4824.2 2173.14  4874.4 2168.77  4884.5 2168.47  4894.5 2169.29
  4954.8  2167.1  5030.7 2167.72  5045.1 2166.93  5059.4 2167.17  5062.2 2166.43
  5062.7 2165.93  5083.4 2165.93  5083.9 2166.43  5086.7 2167.27  5151.1  2170.9
  5179.1 2170.82  5250.7 2173.02  5300.9 2175.69  5378.3 2181.08  5399.1 2183.09
  5491.5 2187.71  5633.4 2189.71    5714 2191.61  5719.5 2191.75    5776 2192.98
#Mann= 6 ,-1 , 0
  4442.7     .07       0  5062.2     .05       0  5083.9     .07       0
  5300.9    .035       0    5714     .07       0  5719.5      .1       0
Bank Sta=5062.2,5083.9
XS Rating Curve= 0 ,0
Exp/Cntr=0.3,0.1

Type RM Length L Ch R = 1 ,139511  ,547,547,547
BEGIN DESCRIPTION:
South Fork Guadalupe River 219.0
END DESCRIPTION:
XS GIS Cut Line= 3
      1798975.01     13893025.03        1798725.       13892475.
      1798324.99     13892174.99
#Sta/Elev= 30
    4400 2193.63    4422 2192.71  4506.6 2184.73  4609.8 2178.77  4673.5 2171.99
  4696.6 2170.33  4748.2 2169.26  4762.5 2169.84  4771.3 2168.98  4784.5 2168.98
  4799.9  2169.5  4806.5 2170.53  4839.4 2170.81  4888.6  2169.2  4927.3 2167.55
  4949.3 2162.66  4949.8 2162.16  4971.1 2162.66  4972.3 2163.93  4982.2 2164.54
  5017.7 2164.64  5040.6 2165.55  5046.9  2167.6  5061.5 2168.76  5082.3 2171.75
  5182.3 2179.09  5246.9 2180.36  5334.2 2183.52  5411.5 2186.22  5504.2 2186.59
#Mann= 5 ,-1 , 0
    4400     .07       0  4888.6    .035       0  4949.3    .035       0
  4971.1    .035       0  5334.2     .07       0
Bank Sta=4949.3,4971.1
XS Rating Curve= 0 ,0
Exp/Cntr=0.3,0.1

Type RM Length L Ch R = 1 ,138964  ,348,348,348
BEGIN DESCRIPTION:
South Fork Guadalupe River 218.0
END DESCRIPTION:
XS GIS Cut Line= 3
      1799075.01     13893074.95        1799225.       13892325.
      1798074.96     13891774.98
#Sta/Elev= 30
  4235.2 2194.98  4259.8 2194.56  4306.5 2192.17  4326.9 2189.81  4388.1 2186.23
  4520.7 2175.79  4614.3 2171.63  4694.1 2168.25  4816.4 2170.24  4899.8 2169.69
  4938.8 2167.42    4949 2165.64  4968.7  2159.8  4969.2  2159.3  4990.5  2159.8
  5008.6 2160.47  5014.1 2162.66  5022.2 2163.18  5053.9 2162.67  5082.1 2164.65
  5121.9 2165.28  5188.4 2169.26    5456 2175.22    5524 2175.45  5586.5 2173.87
  5631.8 2174.72  5809.2 2181.97  5943.2 2184.68    6170 2191.37  6274.8 2192.96
#Mann= 6 ,-1 , 0
  4235.2     .07       0  4259.8      .1       0  4614.3    .035       0
  4899.8     .07       0  4968.7     .05       0  4990.5     .07       0
Bank Sta=4968.7,4990.5
XS Rating Curve= 0 ,0
Exp/Cntr=0.3,0.1

Type RM Length L Ch R = 1 ,138616  ,563,563,563
BEGIN DESCRIPTION:
South Fork Guadalupe River 217.0
END DESCRIPTION:
XS GIS Cut Line= 3
      1799863.01      13892450.5      1799595.59     13892199.85
        1798025.       13891625.
#Sta/Elev= 30
  4552.9 2188.52    4633 2185.41  4711.1 2180.08  4732.2 2177.64  4767.8 2175.22
  4796.1 2170.47  4838.2 2167.22  4866.5 2162.99  4922.4 2162.71  4941.3 2163.41
  4994.6 2161.08  5004.8 2159.82  5005.3 2159.32  5026.9 2159.82  5038.9 2161.81
  5101.1 2165.92  5175.6 2168.44  5186.3 2169.99  5211.4 2171.14  5272.5 2171.77
  5463.1 2171.08  5612.1 2174.69  5857.1 2175.69  5911.9 2177.69  5931.7  2177.6
  5992.9 2180.54  6195.9 2185.16  6304.4 2189.03  6429.4 2192.35  6591.9 2195.25
#Mann= 3 ,-1 , 0
  4552.9     .07       0  5004.8     .05       0  5026.9     .07       0
Bank Sta=5004.8,5026.9
XS Rating Curve= 0 ,0
Exp/Cntr=0.3,0.1

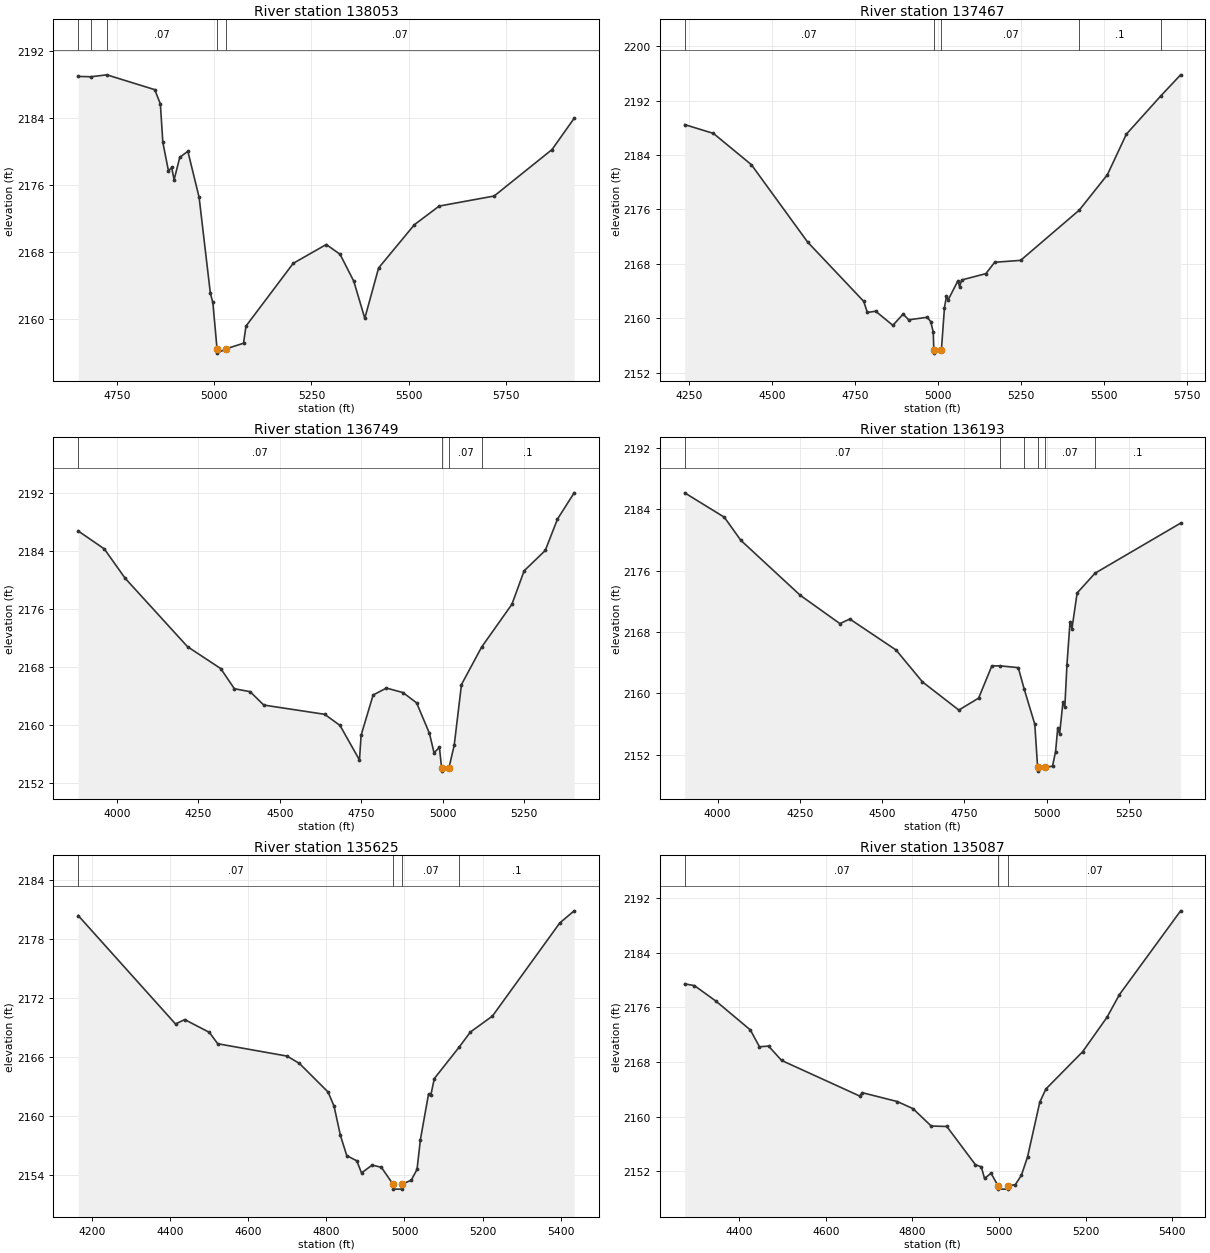
Type RM Length L Ch R = 1 ,138053  ,586,586,586
BEGIN DESCRIPTION:
South Fork Guadalupe River 216.2
END DESCRIPTION:
XS GIS Cut Line= 3
      1800095.54     13891990.37      1799708.81     13891690.16
      1799163.94     13891125.58
#Sta/Elev= 30
  4650.9 2188.92  4683.5 2188.88  4724.4 2189.11  4847.5 2187.34    4862 2185.63
  4868.3 2181.06  4882.8 2177.63    4891 2178.05  4897.3 2176.58  4911.8 2179.26
  4932.6 2179.98  4961.5 2174.49  4990.5    2163  4996.8 2161.93  5007.6 2156.38
  5008.1 2155.88  5029.8 2156.38  5075.6 2157.06    5082 2159.11  5203.3  2166.6
  5288.2 2168.85  5323.7 2167.68  5358.9 2164.47  5387.2 2160.04  5422.7 2166.05
  5514.5 2171.21  5578.3 2173.44  5719.6 2174.64  5868.3 2180.19  5925.1 2183.92
#Mann= 5 ,-1 , 0
  4650.9     .07       0  4683.5      .1       0  4724.4     .07       0
  5007.6     .05       0  5029.8     .07       0
Bank Sta=5007.6,5029.8
XS Rating Curve= 0 ,0
Exp/Cntr=0.3,0.1

Type RM Length L Ch R = 1 ,137467  ,718,718,718
BEGIN DESCRIPTION:
South Fork Guadalupe River 16.1
END DESCRIPTION:
XS GIS Cut Line= 4
      1800146.91     13891795.31       1799962.5     13891258.63
      1799614.53     13891163.17       1799143.9      13890849.3
#Sta/Elev= 30
  4237.8 2188.47  4324.3 2187.18  4438.7 2182.58  4608.2  2171.2  4777.2 2162.48
    4788 2160.85  4813.1 2161.03  4864.9 2158.96    4896 2160.61  4912.5 2159.77
  4968.6 2160.14    4979  2159.5  4986.6 2157.97  4988.3 2155.37  4988.8 2154.87
  5011.2 2155.37  5020.4 2161.54  5026.3 2163.22  5031.5  2162.7  5060.7 2165.49
  5065.9 2164.64  5072.3 2165.63  5145.2 2166.56  5171.7 2168.23  5249.8 2168.51
  5426.5  2175.9  5511.2  2181.1  5568.3 2187.06  5672.6 2192.72  5731.8 2195.79
#Mann= 5 ,-1 , 0
  4237.8     .07       0  4988.3     .05       0  5011.2     .07       0
  5426.5      .1       0  5672.6     .07       0
Bank Sta=4988.3,5011.2
XS Rating Curve= 0 ,0
Exp/Cntr=0.3,0.1

Type RM Length L Ch R = 1 ,136749  ,556,556,556
BEGIN DESCRIPTION:
South Fork Guadalupe River 216.0
END DESCRIPTION:
XS GIS Cut Line= 3
        1800175.     13891675.02        1799975.       13890575.
      1799624.97     13890374.99
#Sta/Elev= 30
  3881.9 2186.81    3962 2184.33  4025.5 2180.29  4217.3  2170.8    4319 2167.78
  4360.9 2164.99  4409.2 2164.58  4451.1 2162.73  4637.9 2161.45  4684.9 2159.91
  4744.6 2155.13  4749.7 2158.57  4786.5 2164.12  4827.2 2165.08    4878 2164.46
  4919.9 2163.03  4959.3 2158.81  4973.3 2156.13  4989.8 2156.87  4996.4 2154.09
  4996.9 2153.59  5019.3 2154.09  5035.2 2157.17  5057.5 2165.57  5119.4 2170.76
  5212.3 2176.68  5249.7  2181.3  5314.5 2184.12    5352 2188.46  5403.1 2192.09
#Mann= 4 ,-1 , 0
  3881.9     .07       0  4996.4     .05       0  5019.3     .07       0
  5119.4      .1       0
Bank Sta=4996.4,5019.3
XS Rating Curve= 0 ,0
Exp/Cntr=0.3,0.1

Type RM Length L Ch R = 1 ,136193  ,568,568,568
BEGIN DESCRIPTION:
South Fork Guadalupe River 215.0
END DESCRIPTION:
XS GIS Cut Line= 3
        1800375.     13891624.96        1800475.       13890525.
        1800275.     13890175.01
#Sta/Elev= 30
  3899.9 2186.16  4020.4 2182.98  4070.6 2179.97  4251.3  2172.8  4371.8 2169.11
  4401.9 2169.71  4542.5 2165.67  4622.8 2161.51  4733.3 2157.84  4793.5  2159.4
  4833.7 2163.61  4859.8  2163.6    4914 2163.37  4932.3 2160.53  4964.2    2156
  4972.8 2150.38  4973.3 2149.88  4995.8 2150.38  5018.1 2150.53  5027.4 2152.43
  5033.9 2155.46  5039.7 2154.76  5049.7 2158.83  5055.5 2158.24    5062 2163.77
  5071.3 2169.33  5077.1 2168.44  5092.9  2173.1  5147.3 2175.68  5407.5 2182.21
#Mann= 6 ,-1 , 0
  3899.9     .07       0  4859.8      .1       0  4932.3     .07       0
  4972.8     .05       0  4995.8     .07       0  5147.3      .1       0
Bank Sta=4972.8,4995.8
XS Rating Curve= 0 ,0
Exp/Cntr=0.3,0.1

Type RM Length L Ch R = 1 ,135625  ,538,538,538
BEGIN DESCRIPTION:
South Fork Guadalupe River 214.0
END DESCRIPTION:
XS GIS Cut Line= 3
      1800724.99     13891525.03        1800975.       13890725.
        1801225.       13890375.
#Sta/Elev= 30
  4165.7 2180.38  4414.6 2169.34  4438.1 2169.79    4501 2168.49  4522.5 2167.33
  4700.1 2166.07  4731.5 2165.32  4804.8 2162.41    4820 2160.97  4836.3 2157.99
  4852.5 2155.94  4878.2 2155.41  4890.2 2154.18  4917.5 2154.98    4941 2154.75
  4970.8 2153.03  4971.3 2152.53  4993.5 2152.53    4994 2153.03  5017.4 2153.44
  5032.2 2154.54  5040.8 2157.57  5061.6 2162.21  5067.8 2162.16  5076.4 2163.79
  5139.6 2166.97  5168.6 2168.52  5225.1 2170.15  5397.1 2179.62    5434 2180.86
#Mann= 4 ,-1 , 0
  4165.7     .07       0  4970.8     .05       0    4994     .07       0
  5139.6      .1       0
Bank Sta=4970.8,4994
XS Rating Curve= 0 ,0
Exp/Cntr=0.3,0.1

Type RM Length L Ch R = 1 ,135087  ,514,514,514
BEGIN DESCRIPTION:
South Fork Guadalupe River 213.0
END DESCRIPTION:
XS GIS Cut Line= 3
      1801025.03     13891574.96        1801425.       13890975.
      1801724.98     13890675.02
#Sta/Elev= 30
  4274.3 2179.45  4296.8 2179.19  4346.4 2176.93    4426  2172.7    4447 2170.24
  4468.1 2170.34  4498.1 2168.24  4678.4 2163.03  4684.4 2163.52  4765.5 2162.22
  4801.6 2161.18  4843.6 2158.64  4879.7 2158.57  4945.8 2152.97  4959.3 2152.66
  4966.8 2150.96  4981.8 2151.73  4997.8  2149.9  4998.3  2149.4  5020.7  2149.4
  5021.2  2149.9  5037.8 2150.05  5051.9 2151.43  5066.1 2154.12  5094.4 2162.14
  5108.5 2164.06  5193.4 2169.52  5249.9 2174.59  5278.2 2177.87  5419.6 2190.14
#Mann= 3 ,-1 , 0
  4274.3     .07       0  4997.8     .05       0  5021.2     .07       0
Bank Sta=4997.8,5021.2
XS Rating Curve= 0 ,0
Exp/Cntr=0.3,0.1

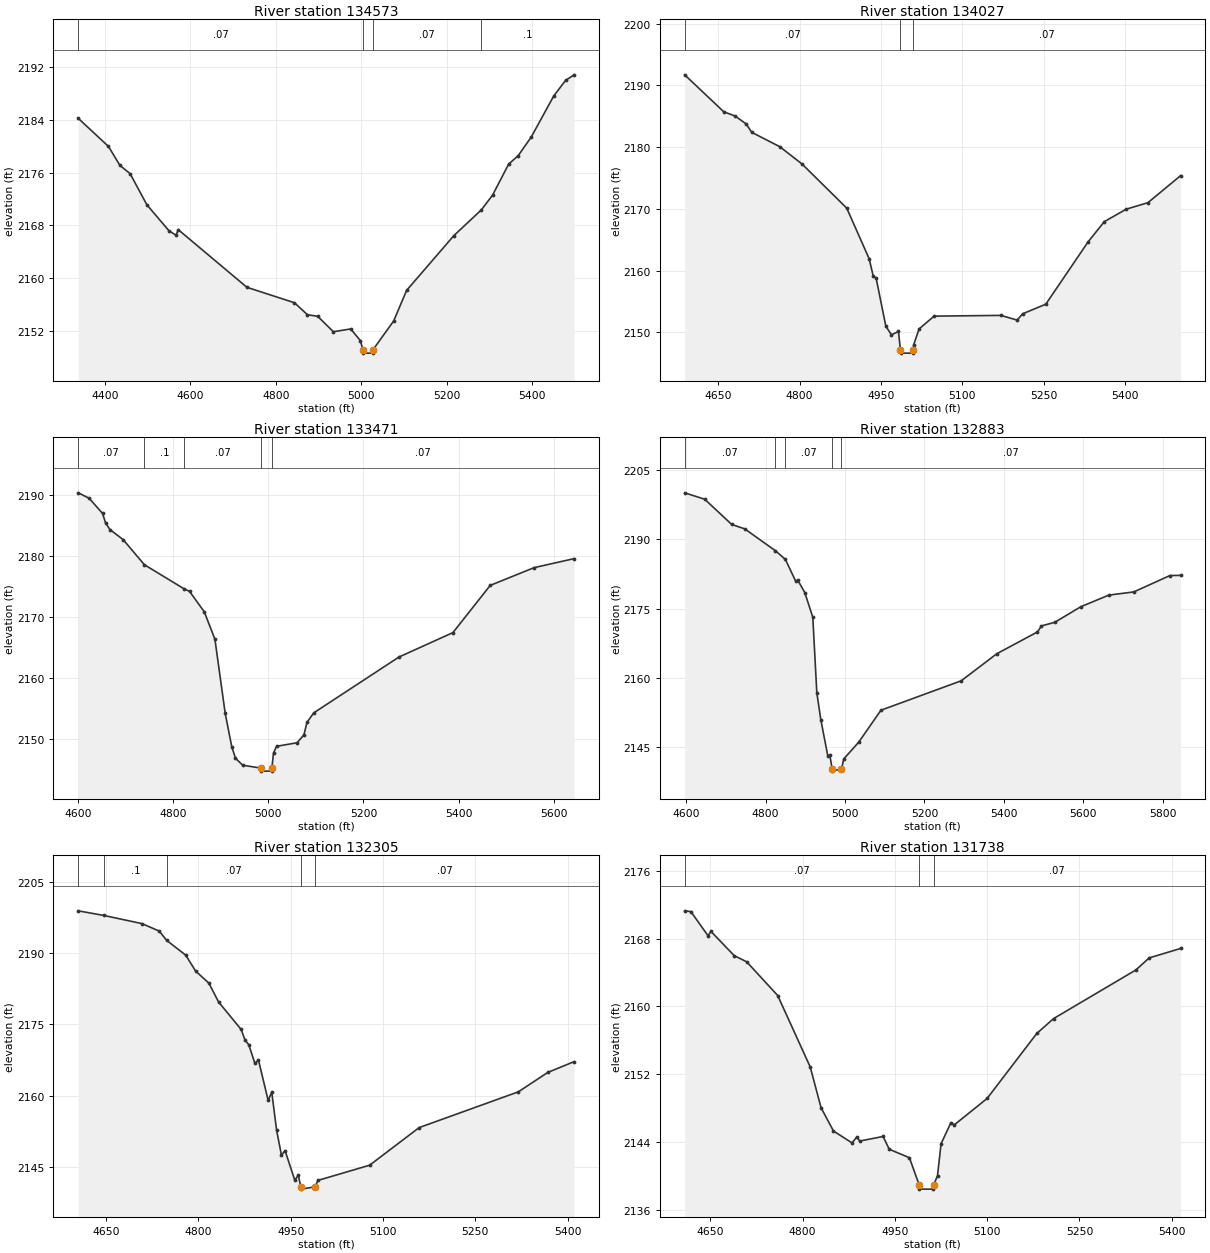
Type RM Length L Ch R = 1 ,134573  ,546,546,546
BEGIN DESCRIPTION:
South Fork Guadalupe River 212.0
END DESCRIPTION:
XS GIS Cut Line= 3
        1801975.     13891824.97        1801875.       13891175.
        1801825.     13890675.01
#Sta/Elev= 30
  4337.5 2184.27  4408.3 2179.99  4434.9 2177.12  4458.9 2175.85  4498.1 2171.12
  4549.9 2167.16  4566.4 2166.49  4571.4 2167.34  4732.1 2158.57  4843.4 2156.22
  4873.7  2154.4  4897.7 2154.16  4934.4 2151.81  4974.9 2152.24  4997.6 2150.46
  5003.5 2149.06    5004 2148.56  5026.4 2148.56  5026.9 2149.06  5075.5 2153.46
  5105.7  2158.1  5216.2 2166.43  5280.5 2170.34  5306.7 2172.58  5344.4  2177.3
    5367 2178.61  5397.1 2181.41  5449.9 2187.67  5477.5 2190.03  5497.6 2190.88
#Mann= 4 ,-1 , 0
  4337.5     .07       0  5003.5     .05       0  5026.9     .07       0
  5280.5      .1       0
Bank Sta=5003.5,5026.9
XS Rating Curve= 0 ,0
Exp/Cntr=0.3,0.1

Type RM Length L Ch R = 1 ,134027  ,556,556,556
BEGIN DESCRIPTION:
South Fork Guadalupe River 211.0
END DESCRIPTION:
XS GIS Cut Line= 3
      1802425.01     13891825.02        1802325.       13891425.
        1802275.     13890925.03
#Sta/Elev= 30
  4588.1 2191.69  4660.3  2185.7  4680.9 2185.03  4701.5 2183.74  4711.8 2182.38
  4763.4 2180.06  4804.6 2177.25    4887 2170.11  4928.3 2161.93    4936 2159.07
  4941.2 2158.79  4959.2 2150.98  4969.5 2149.59  4982.4 2150.14  4986.1 2147.13
  4986.6 2146.63  5009.1 2146.63  5009.6 2147.13  5010.5 2147.98  5020.5 2150.55
  5048.2 2152.62  5171.3 2152.74  5201.4 2151.98  5211.5    2153  5254.2 2154.55
  5332.1 2164.63  5362.2 2167.92  5402.4 2169.93  5442.6 2170.99  5502.9 2175.37
#Mann= 3 ,-1 , 0
  4588.1     .07       0  4986.1     .05       0  5009.6     .07       0
Bank Sta=4986.1,5009.6
XS Rating Curve= 0 ,0
Exp/Cntr=0.3,0.1

Type RM Length L Ch R = 1 ,133471  ,588,588,588
BEGIN DESCRIPTION:
South Fork Guadalupe River 210.0
END DESCRIPTION:
XS GIS Cut Line= 3
      1803074.97     13891374.98        1802725.       13891175.
      1802229.74     13890771.51
#Sta/Elev= 30
  4600.9 2190.32  4623.9 2189.43    4652 2186.95  4658.5 2185.37  4667.8 2184.29
  4695.2 2182.68  4739.9 2178.56  4823.5 2174.61  4834.8  2174.2  4865.8 2170.85
  4888.1 2166.37  4909.7 2154.25  4923.4 2148.82  4931.3 2146.91  4946.4 2145.77
  4984.3  2145.3  4984.8  2144.8  5007.3  2144.8  5007.8  2145.3  5011.2 2147.76
  5017.6 2148.86  5060.7 2149.44  5075.1 2150.73  5081.5 2152.78  5095.9 2154.34
  5274.7 2163.46  5388.2 2167.46  5466.5 2175.18  5558.6 2178.08  5642.8 2179.56
#Mann= 5 ,-1 , 0
  4600.9     .07       0  4739.9      .1       0  4823.5     .07       0
  4984.3     .05       0  5007.8     .07       0
Bank Sta=4984.3,5007.8
XS Rating Curve= 0 ,0
Exp/Cntr=0.3,0.1

Type RM Length L Ch R = 1 ,132883  ,578,578,578
BEGIN DESCRIPTION:
South Fork Guadalupe River 209.0
END DESCRIPTION:
XS GIS Cut Line= 3
      1803374.98       13890775.        1802975.       13890725.
      1802138.42     13890604.61
#Sta/Elev= 30
  4596.5 2199.98  4646.9  2198.6  4714.9 2193.15  4747.7  2192.2  4824.9 2187.47
  4849.9 2185.61  4876.1 2180.86  4881.2 2181.11  4898.8 2178.45    4919  2173.1
  4929.1 2156.82  4939.1 2151.01  4956.8 2143.15  4961.8 2143.39  4967.6 2140.38
  4968.1 2139.88  4991.2 2140.38  4997.1 2142.53  5034.8 2146.16  5090.5 2153.03
  5292.6 2159.39  5382.1 2165.23  5484.5 2169.94  5494.6 2171.24  5528.1 2172.02
  5593.5 2175.38    5664 2177.89    5727 2178.58  5817.9 2182.12  5844.8 2182.15
#Mann= 5 ,-1 , 0
  4596.5     .07       0  4824.9      .1       0  4849.9     .07       0
  4967.6     .05       0  4991.2     .07       0
Bank Sta=4967.6,4991.2
XS Rating Curve= 0 ,0
Exp/Cntr=0.3,0.1

Type RM Length L Ch R = 1 ,132305  ,567,567,567
BEGIN DESCRIPTION:
South Fork Guadalupe River 208.0
END DESCRIPTION:
XS GIS Cut Line= 3
      1803225.02     13890375.01        1802875.       13890175.
      1802475.05     13890224.99
#Sta/Elev= 30
  4604.6  2198.9  4646.5 2197.92  4708.3 2196.21  4736.4 2194.63  4748.2 2192.71
  4779.5 2189.56  4795.4 2186.23    4817 2183.69  4832.8 2179.72  4869.5 2173.94
    4876 2171.63  4881.8 2170.75  4891.8  2166.8  4897.6 2167.52  4913.4    2159
  4919.2 2160.76  4927.1 2152.74    4935 2147.48  4940.8 2148.47  4956.6 2142.25
  4962.4 2143.26  4966.4 2140.85  4966.9 2140.35    4990 2140.85  4994.1 2142.18
  5078.3 2145.38  5158.9  2153.3  5320.1 2160.82    5368 2164.91  5410.8 2167.17
#Mann= 5 ,-1 , 0
  4604.6     .07       0  4646.5      .1       0  4748.2     .07       0
  4966.4     .05       0    4990     .07       0
Bank Sta=4966.4,4990
XS Rating Curve= 0 ,0
Exp/Cntr=0.3,0.1

Type RM Length L Ch R = 1 ,131738  ,540,540,540
BEGIN DESCRIPTION:
South Fork Guadalupe River 207.0
END DESCRIPTION:
XS GIS Cut Line= 3
      1803024.99       13889675.        1802625.       13889725.
      1802275.02     13889924.99
#Sta/Elev= 30
  4608.2 2171.26  4618.3 2171.17    4646 2168.34    4651 2168.83  4688.8 2165.98
    4709 2165.26  4759.4 2161.29  4812.3 2152.88  4829.9 2148.08  4850.1 2145.34
  4880.3 2143.94  4887.9 2144.63  4892.9 2144.16  4930.7  2144.7  4940.8 2143.19
  4973.5  2142.2  4989.4    2139  4989.9  2138.5  5012.5  2138.5    5013    2139
  5019.2 2140.09    5025 2143.85  5040.8 2146.29  5046.6 2146.07  5099.8 2149.17
  5180.5 2156.82  5207.8 2158.57  5341.7  2164.3  5363.3 2165.72  5414.4 2166.83
#Mann= 3 ,-1 , 0
  4608.2     .07       0  4989.4     .05       0    5013     .07       0
Bank Sta=4989.4,5013
XS Rating Curve= 0 ,0
Exp/Cntr=0.3,0.1

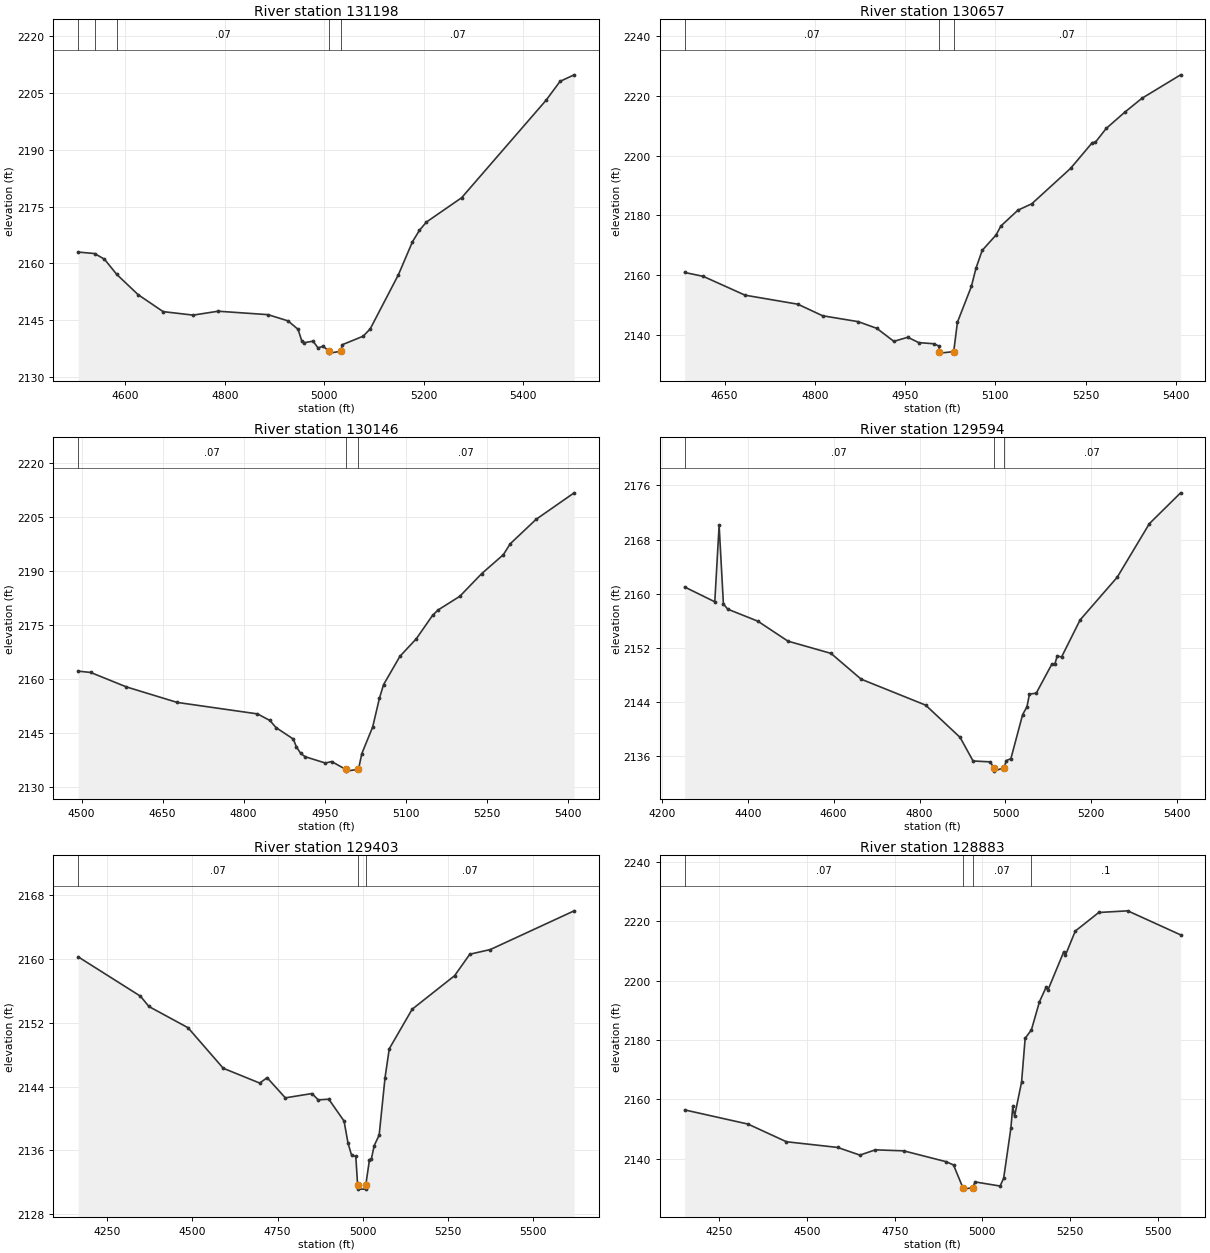
Type RM Length L Ch R = 1 ,131198  ,541,541,541
BEGIN DESCRIPTION:
South Fork Guadalupe River 206.0
END DESCRIPTION:
XS GIS Cut Line= 3
      1802824.95       13889275.        1802325.       13889325.
      1801975.02     13888975.02
#Sta/Elev= 30
  4505.3 2162.97  4538.2 2162.58    4558  2161.1  4582.9 2157.06  4625.9 2151.71
  4676.1 2147.24  4736.4 2146.32  4786.7 2147.35  4887.1 2146.44  4927.3 2144.79
  4947.4 2142.57    4955 2139.48    4960 2139.04  4977.6 2139.44  4987.6 2137.66
  4997.7 2138.09    5010 2136.78  5010.5 2136.28  5033.7 2136.78    5036 2138.48
  5078.5 2140.76  5092.6  2142.7  5149.2 2156.97  5177.5 2165.68  5191.6 2168.73
  5205.7 2170.91  5276.4 2177.32  5446.2 2203.06  5474.4 2208.06  5502.7 2209.78
#Mann= 5 ,-1 , 0
  4505.3     .07       0  4538.2      .1       0  4582.9     .07       0
    5010     .05       0  5033.7     .07       0
Bank Sta=5010,5033.7
XS Rating Curve= 0 ,0
Exp/Cntr=0.3,0.1

Type RM Length L Ch R = 1 ,130657  ,511,511,511
BEGIN DESCRIPTION:
South Fork Guadalupe River 205.0
END DESCRIPTION:
XS GIS Cut Line= 3
      1802824.96     13888974.99        1802425.       13888875.
      1802024.98       13888775.
#Sta/Elev= 30
  4583.5 2160.98  4614.4 2159.68    4684  2153.4  4771.6  2150.4  4812.8 2146.54
  4872.1 2144.57    4903 2142.33  4931.3    2138  4954.5 2139.37  4972.6 2137.58
  4998.3 2137.19  5006.1 2136.42  5007.1 2134.57  5007.6 2134.07  5030.8 2134.57
    5037 2144.38  5060.2 2156.32  5067.9 2162.44  5078.2 2168.35  5101.4 2173.53
  5109.2 2176.47  5137.5 2181.75  5160.7 2183.91  5225.1  2195.7  5261.2 2204.29
  5266.3  2204.4  5284.4 2209.04  5315.3 2214.46  5343.7 2219.08  5408.1 2226.92
#Mann= 3 ,-1 , 0
  4583.5     .07       0  5007.1     .05       0  5030.8     .07       0
Bank Sta=5007.1,5030.8
XS Rating Curve= 0 ,0
Exp/Cntr=0.3,0.1

Type RM Length L Ch R = 1 ,130146  ,552,552,552
BEGIN DESCRIPTION:
South Fork Guadalupe River 204.0
END DESCRIPTION:
XS GIS Cut Line= 3
      1802925.01     13888925.02        1802675.       13888475.
      1802275.02       13888425.
#Sta/Elev= 30
  4493.9 2162.17  4516.8 2161.82  4583.2 2157.79    4677 2153.49  4825.7  2150.3
  4848.6 2148.48    4860  2146.5    4892 2143.31  4897.7 2141.14  4905.7 2139.33
  4913.8 2138.41  4951.5 2136.64  4962.9 2137.07  4988.8  2134.9  4989.3  2134.4
  5012.6  2134.9  5018.8 2139.26  5038.9 2146.67  5051.5  2154.7  5059.1 2158.44
  5089.3 2166.29  5119.6 2171.16  5149.8 2177.68  5159.9 2179.16  5200.2 2182.97
  5240.5 2189.24  5280.8 2194.53  5293.4 2197.54  5341.3 2204.34  5411.8 2211.71
#Mann= 3 ,-1 , 0
  4493.9     .07       0  4988.8     .05       0  5012.6     .07       0
Bank Sta=4988.8,5012.6
XS Rating Curve= 0 ,0
Exp/Cntr=0.3,0.1

Type RM Length L Ch R = 1 ,129594  ,191,191,191
BEGIN DESCRIPTION:
South Fork Guadalupe River 203.0
END DESCRIPTION:
XS GIS Cut Line= 3
        1803025.     13888874.99        1803075.       13888125.
      1802724.97     13887924.98
#Sta/Elev= 30
  4253.1 2160.98  4323.2  2158.8  4333.3 2170.08  4343.3 2158.47  4353.3 2157.71
  4423.5 2155.93  4493.6 2152.98  4593.8 2151.17    4664 2147.36  4814.3 2143.52
  4894.5 2138.75  4924.6 2135.27  4964.7 2135.14  4972.8 2134.27  4973.3 2133.77
  4996.6 2134.27  5002.2 2135.33  5012.7 2135.62    5040 2142.12  5050.1 2143.28
  5055.9 2145.15  5071.7 2145.29  5108.4 2149.62  5114.9 2149.57  5120.6 2150.79
  5130.7 2150.64  5173.9 2156.12  5260.3 2162.43  5335.2 2170.35  5407.9  2174.9
#Mann= 3 ,-1 , 0
  4253.1     .07       0  4972.8     .05       0  4996.6     .07       0
Bank Sta=4972.8,4996.6
XS Rating Curve= 0 ,0
Exp/Cntr=0.3,0.1

Type RM Length L Ch R = 1 ,129403  ,520,520,520
BEGIN DESCRIPTION:
Mapping XS afeae630
END DESCRIPTION:
XS GIS Cut Line= 5
      1803033.06     13888857.86      1803078.74     13888686.39
      1803284.61     13888150.24      1803160.31      13887885.2
      1802784.05     13887722.84
#Sta/Elev= 30
  4165.2 2160.25  4347.8 2155.32  4372.5 2154.03  4487.2 2151.37  4590.5 2146.29
  4697.6 2144.43  4719.1 2145.11  4772.6 2142.58  4850.6 2143.12    4869 2142.33
    4900 2142.41  4944.8 2139.67  4956.4  2136.9  4966.9 2135.38  4979.2 2135.24
  4984.6 2131.64  4985.1 2131.14  5007.9 2131.14  5008.4 2131.64  5019.3 2134.82
  5024.9 2134.93  5033.2  2136.6  5047.7 2137.91    5065 2145.13  5077.4 2148.74
  5144.5 2153.69  5268.9 2157.89  5313.5 2160.58  5373.8 2161.17  5619.5 2166.02
#Mann= 3 ,-1 , 0
  4165.2     .07       0  4984.6     .05       0  5008.4     .07       0
Bank Sta=4984.6,5008.4
XS Rating Curve= 0 ,0
Exp/Cntr=0.3,0.1

Type RM Length L Ch R = 1 ,128883  ,430,430,430
BEGIN DESCRIPTION:
South Fork Guadalupe River 202.0
END DESCRIPTION:
XS GIS Cut Line= 4
      1803075.01     13888724.99      1803410.22     13888192.55
        1803975.       13888075.      1804155.67     13887971.04
#Sta/Elev= 30
  4150.9 2156.47  4331.6 2151.69  4441.1 2145.74  4587.1 2143.83  4650.7 2141.24
  4694.5 2143.01  4775.5 2142.68  4897.3    2139  4917.7 2137.91  4944.3 2130.28
  4944.8 2129.78  4972.9 2130.28    4979 2132.21  5050.5 2130.82  5060.7 2133.44
  5081.2 2150.25  5086.7 2157.64  5091.8 2154.36  5111.8 2165.85    5122  2180.6
  5139.8 2183.41  5162.9 2192.94  5181.7 2197.78  5186.8  2196.8  5231.8 2209.64
  5236.9 2208.61    5265 2216.71  5331.9 2222.97  5414.6 2223.53  5565.4 2215.43
#Mann= 4 ,-1 , 0
  4150.9     .07       0  4944.3     .05       0  4972.9     .07       0
  5139.8      .1       0
Bank Sta=4944.3,4972.9
XS Rating Curve= 0 ,0
Exp/Cntr=0.3,0.1

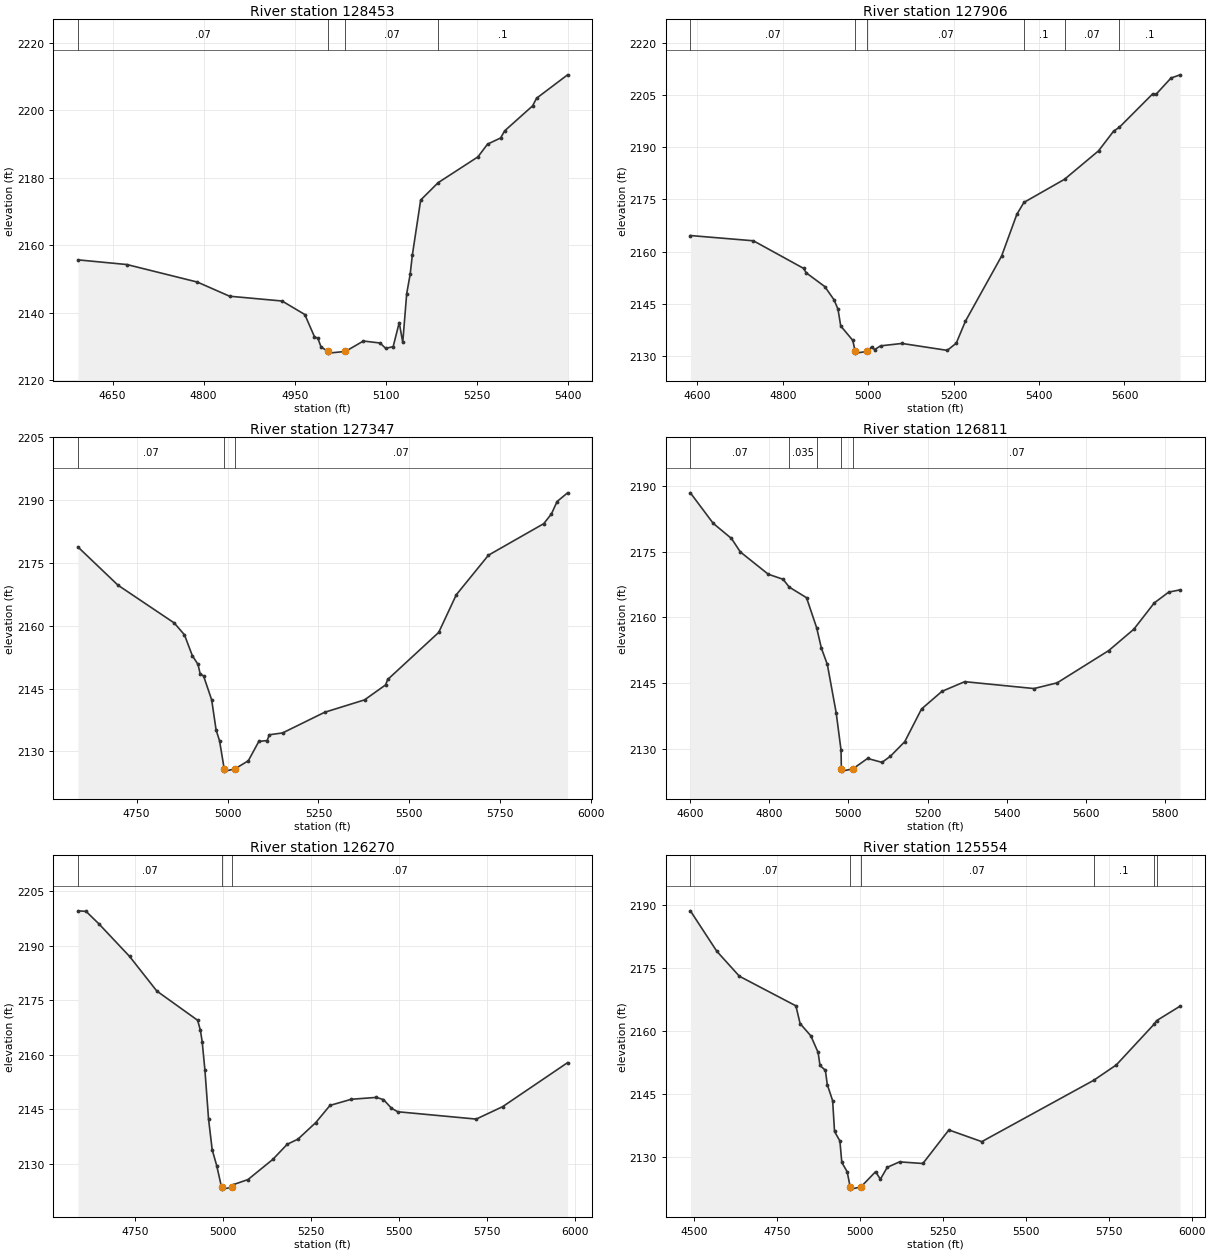
Type RM Length L Ch R = 1 ,128453  ,547,547,547
BEGIN DESCRIPTION:
South Fork Guadalupe River 201.0
END DESCRIPTION:
XS GIS Cut Line= 3
      1803124.96     13888725.02        1803475.       13888525.
      1803825.02     13888324.99
#Sta/Elev= 30
    4593 2155.67  4673.7 2154.28  4789.6 2149.09  4842.8 2144.89  4929.2 2143.47
  4966.6 2139.47  4982.5 2132.89  4988.2 2132.38  4993.3 2129.87  5004.9 2128.52
  5005.4 2128.02  5033.5 2128.52  5063.1 2131.61  5090.5 2131.02  5099.8 2129.44
  5112.1 2129.93  5122.1 2137.08  5127.9 2131.19  5134.4 2145.66  5140.1 2151.37
  5143.7 2157.08  5157.4  2173.4  5186.1 2178.54  5251.7  2186.2  5267.5 2189.97
  5289.1 2191.81  5295.6  2193.9  5341.7 2201.32  5348.2 2203.58  5399.3 2210.52
#Mann= 4 ,-1 , 0
    4593     .07       0  5004.9     .05       0  5033.5     .07       0
  5186.1      .1       0
Bank Sta=5004.9,5033.5
XS Rating Curve= 0 ,0
Exp/Cntr=0.3,0.1

Type RM Length L Ch R = 1 ,127906  ,559,559,559
BEGIN DESCRIPTION:
South Fork Guadalupe River 200.0
END DESCRIPTION:
XS GIS Cut Line= 3
        1803125.       13889175.        1803475.       13888975.
      1804024.99     13888475.01
#Sta/Elev= 30
  4583.7 2164.63  4731.3 2163.12  4848.6 2155.21  4855.1  2153.9  4898.3 2149.98
  4919.9 2146.19  4929.2 2143.52  4935.7 2138.66  4963.8 2134.54  4969.6 2131.36
  4970.1 2130.86  4998.2 2131.36  5008.1 2132.68  5014.9 2131.87    5029 2132.95
    5079 2133.64  5185.1 2131.65  5206.1 2133.71  5227.7 2140.05  5312.2  2158.7
    5348 2170.73  5364.6 2174.14  5459.6 2180.78  5539.2 2188.95  5574.4 2194.58
  5588.2 2195.74  5666.3 2205.35  5673.7 2205.17  5708.8 2209.85  5730.1 2210.78
#Mann= 6 ,-1 , 0
  4583.7     .07       0  4969.6     .05       0  4998.2     .07       0
  5364.6      .1       0  5459.6     .07       0  5588.2      .1       0
Bank Sta=4969.6,4998.2
XS Rating Curve= 0 ,0
Exp/Cntr=0.3,0.1

Type RM Length L Ch R = 1 ,127347  ,536,536,536
BEGIN DESCRIPTION:
South Fork Guadalupe River 199.0
END DESCRIPTION:
XS GIS Cut Line= 3
      1803424.98     13889825.04        1803625.       13889475.
      1804125.03     13888674.96
#Sta/Elev= 30
  4588.4 2178.83  4698.6  2169.7  4853.3 2160.68  4881.4 2157.85    4903 2152.89
  4918.8 2150.77  4924.6 2148.54    4934 2148.02  4956.3 2142.31  4968.5  2135.1
  4977.9 2132.56  4990.8  2125.8  4991.3  2125.3  5019.4  2125.8    5057 2127.77
  5085.9 2132.39  5108.9  2132.6  5114.8 2133.98  5151.3 2134.42  5266.9 2139.35
  5376.6 2142.31  5434.4 2145.88  5440.3 2147.18  5580.6 2158.42  5628.9  2167.4
  5717.4 2176.86  5869.5 2184.39  5890.7 2186.73  5906.1 2189.67    5935 2191.75
#Mann= 3 ,-1 , 0
  4588.4     .07       0  4990.8     .05       0  5019.4     .07       0
Bank Sta=4990.8,5019.4
XS Rating Curve= 0 ,0
Exp/Cntr=0.3,0.1

Type RM Length L Ch R = 1 ,126811  ,541,541,541
BEGIN DESCRIPTION:
South Fork Guadalupe River 198.0
END DESCRIPTION:
XS GIS Cut Line= 3
      1803524.99       13890075.        1803875.       13889875.
      1804325.01     13889174.99
#Sta/Elev= 30
  4601.7 2188.43  4659.3 2181.46  4705.4    2178  4727.7 2174.93  4798.2 2169.84
  4835.7 2168.68  4850.9 2166.91  4894.7 2164.48  4920.3  2157.6  4932.1 2152.98
  4947.2 2149.24  4969.5  2138.2  4981.8 2129.65  4982.6 2125.37  4983.1 2124.87
  5011.3 2125.37  5048.7 2127.77  5085.1 2126.87  5106.2 2128.26  5142.5  2131.6
  5184.8 2139.06  5236.3 2143.09  5293.8  2145.3  5468.5 2143.73  5526.9 2145.03
    5657  2152.4  5720.4 2157.28  5771.9 2163.28  5808.3 2165.75    5837 2166.27
#Mann= 5 ,-1 , 0
  4601.7     .07       0  4850.9    .035       0  4920.3     .07       0
  4982.6     .05       0  5011.3     .07       0
Bank Sta=4982.6,5011.3
XS Rating Curve= 0 ,0
Exp/Cntr=0.3,0.1

Type RM Length L Ch R = 1 ,126270  ,716,716,716
BEGIN DESCRIPTION:
South Fork Guadalupe River 197.0
END DESCRIPTION:
XS GIS Cut Line= 3
        1804125.     13890674.99        1804225.       13890275.
      1804379.33     13889308.65
#Sta/Elev= 30
    4588 2199.66  4611.2 2199.51  4647.3 2196.11  4734.9 2187.09  4812.2 2177.57
  4928.1 2169.52  4935.9 2166.77    4941 2163.66  4948.8 2155.81  4959.1 2142.34
  4969.4 2133.89  4982.3 2129.48  4996.1 2123.52  4996.6 2123.02  5024.8 2123.52
  5028.8 2124.24  5071.2 2125.66  5142.1 2131.25  5182.6 2135.38    5213 2136.78
  5263.6 2141.34  5304.1 2146.08  5364.9 2147.77  5435.7 2148.28    5456 2147.68
  5478.6 2145.31  5496.5 2144.33  5719.3 2142.31  5794.1 2145.71  5978.9 2157.85
#Mann= 3 ,-1 , 0
    4588     .07       0  4996.1     .05       0  5024.8     .07       0
Bank Sta=4996.1,5024.8
XS Rating Curve= 0 ,0
Exp/Cntr=0.3,0.1

Type RM Length L Ch R = 1 ,125554  ,622,622,622
BEGIN DESCRIPTION:
South Fork Guadalupe River 196.0
END DESCRIPTION:
XS GIS Cut Line= 3
      1804425.03     13890724.98      1804863.11     13890488.67
      1805474.98     13889725.02
#Sta/Elev= 30
  4488.8  2188.6  4568.3 2178.98  4636.5 2173.01  4806.9 2165.95  4819.6 2161.72
    4852 2158.79  4873.9 2154.83  4879.6 2151.73  4895.8 2150.58  4901.5 2147.19
  4917.7 2143.33  4923.4 2135.99  4939.6 2133.73  4945.3 2128.62  4961.5  2126.4
  4970.6 2122.75  4971.1 2122.25  5002.6 2122.75  5047.2 2126.41  5061.6 2124.62
  5082.4 2127.45  5119.3 2128.75  5189.7 2128.36  5268.1 2136.36  5367.3 2133.57
  5704.8  2148.2  5772.9 2151.86  5886.6 2161.55  5894.2 2162.41  5965.1 2165.87
#Mann= 6 ,-1 , 0
  4488.8     .07       0  4970.6     .05       0  5002.6     .07       0
  5704.8      .1       0  5886.6     .07       0  5894.2      .1       0
Bank Sta=4970.6,5002.6
XS Rating Curve= 0 ,0
Exp/Cntr=0.3,0.1