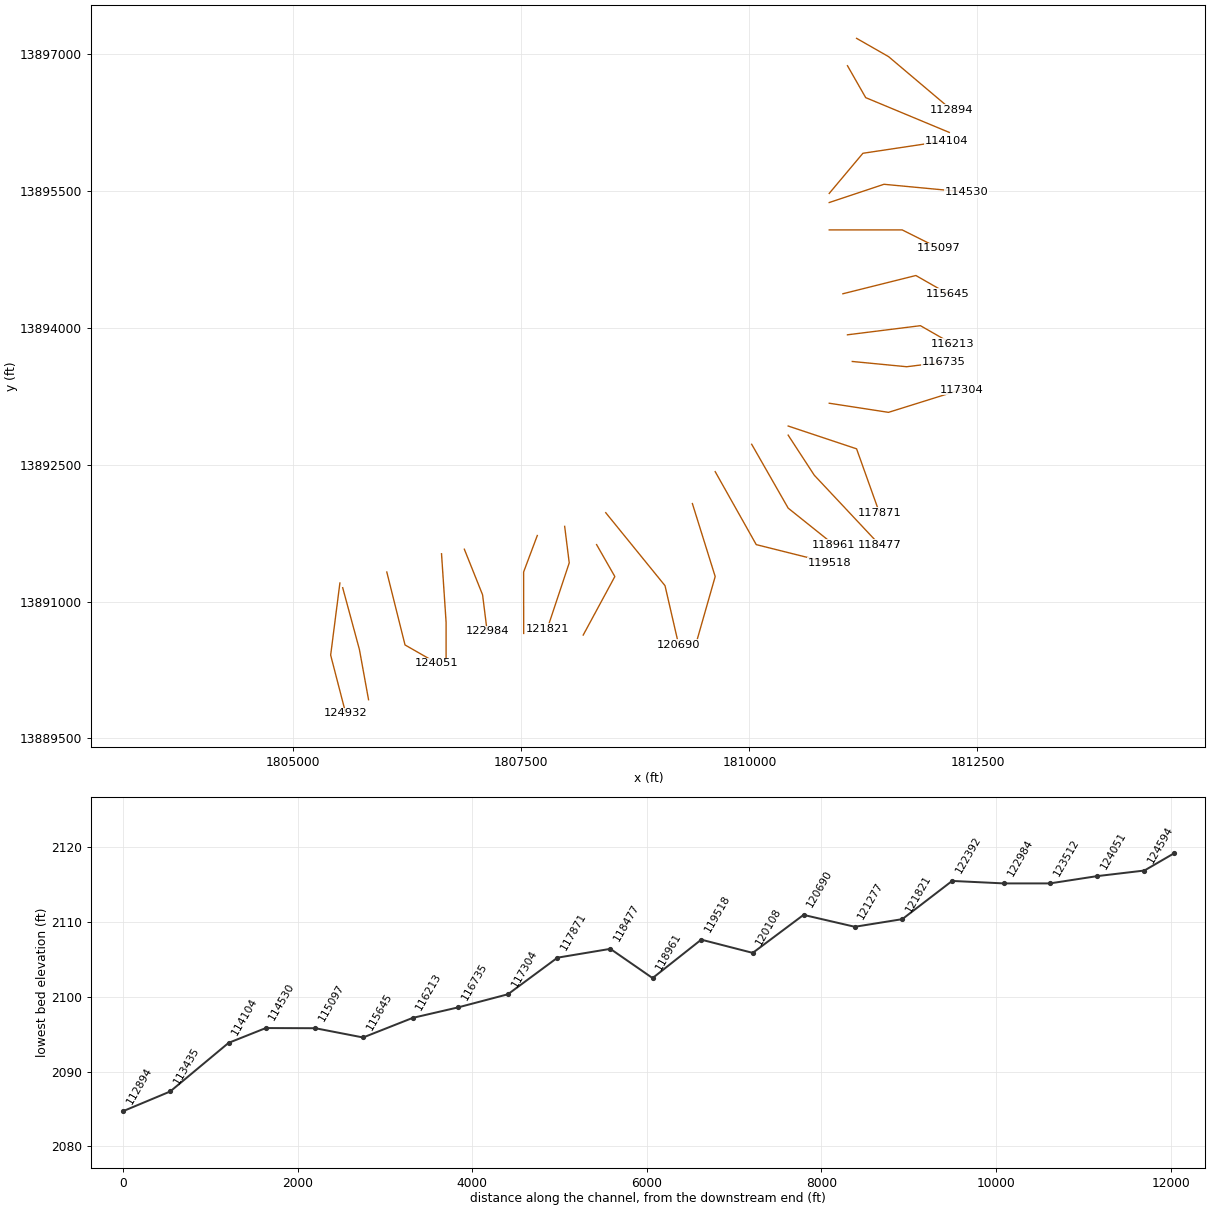
HEC-RAS study South Fork Guadalupe River.prj: South Fork Guadalupe River Base Level Engineering

--- South Fork Guadalupe River.g01 (geometry) --- (continued)

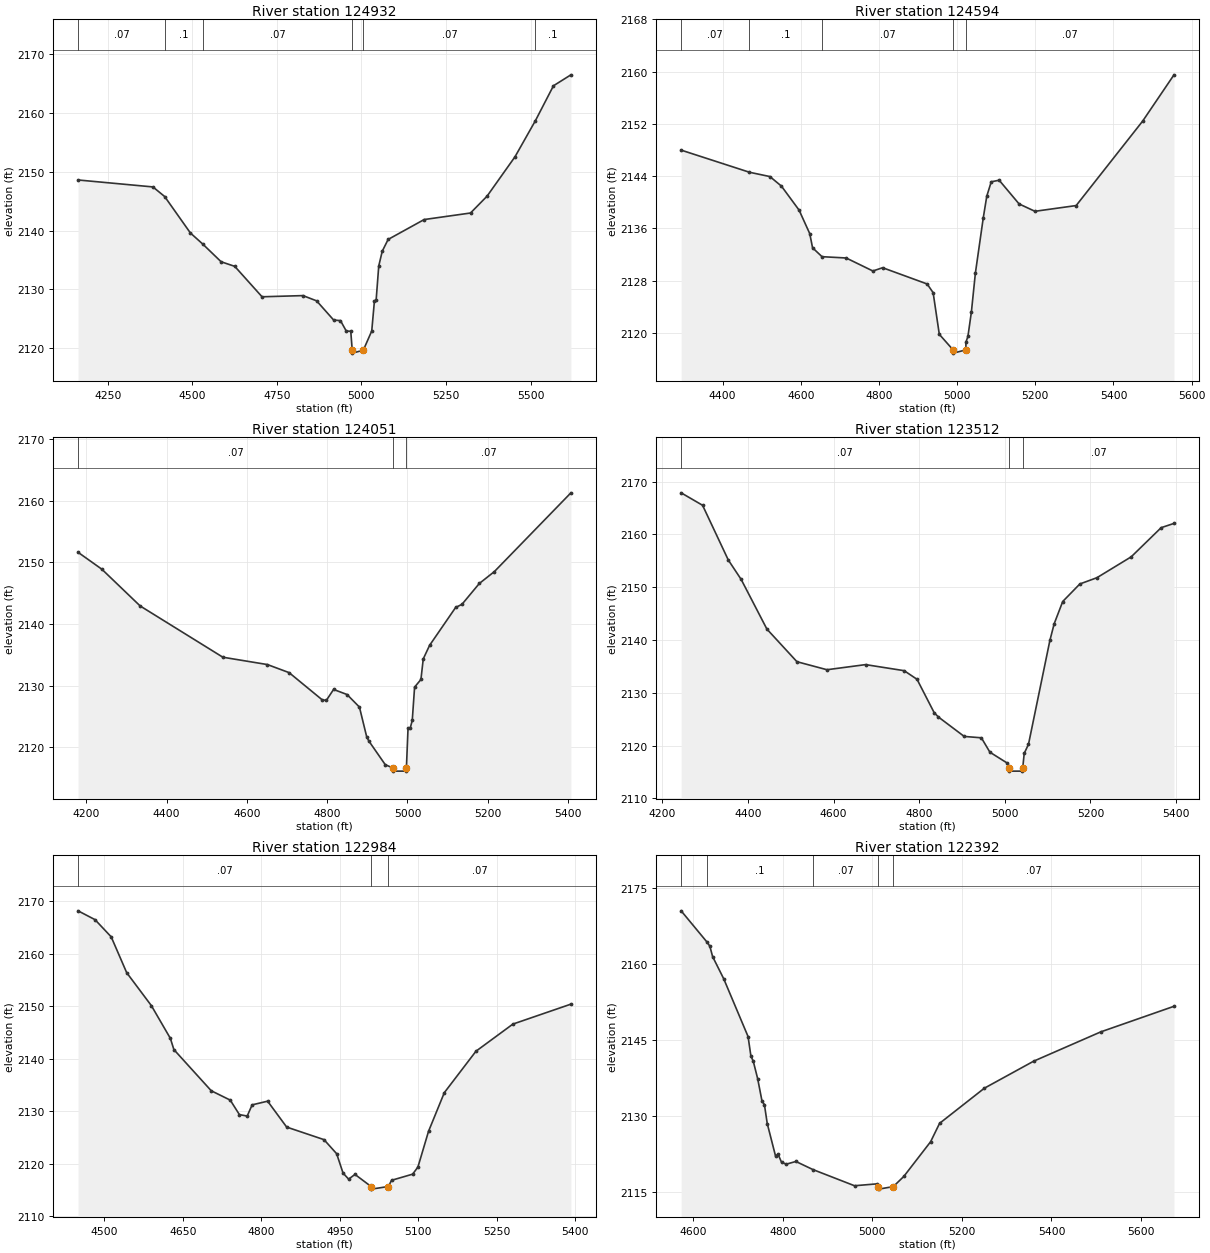
Type RM Length L Ch R = 1 ,124932  ,338,338,338
BEGIN DESCRIPTION:
South Fork Guadalupe River 195.0
END DESCRIPTION:
XS GIS Cut Line= 3
      1805510.97     13891204.48      1805409.62     13890413.53
        1805575.     13889775.01
#Sta/Elev= 30
  4162.4 2148.59  4383.7 2147.41  4418.4 2145.78  4494.6 2139.58  4530.4 2137.74
  4585.3  2134.7  4625.6 2133.92  4706.3 2128.75  4827.3 2128.95  4867.6 2128.06
    4918  2124.8  4938.2  2124.7  4955.1 2122.95  4968.6 2122.88  4972.9 2119.68
  4973.5 2119.18  5005.7 2119.68  5030.6 2122.94  5038.4 2127.96  5043.6 2128.18
  5051.3 2133.98  5061.6 2136.48    5079 2138.49  5185.6 2141.87  5322.6 2142.98
  5371.5 2145.84  5454.1 2152.53  5514.7 2158.69  5567.8 2164.59  5619.4 2166.45
#Mann= 6 ,-1 , 0
  4162.4     .07       0  4418.4      .1       0  4530.4     .07       0
  4972.9     .05       0  5005.7     .07       0  5514.7      .1       0
Bank Sta=4972.9,5005.7
XS Rating Curve= 0 ,0
Exp/Cntr=0.3,0.1

Type RM Length L Ch R = 1 ,124594  ,543,543,543
BEGIN DESCRIPTION:
South Fork Guadalupe River 194.0
END DESCRIPTION:
XS GIS Cut Line= 3
      1805541.58     13891152.65        1805725.       13890475.
      1805825.01     13889924.95
#Sta/Elev= 30
  4293.7 2147.98  4468.5 2144.59  4520.8 2143.93  4550.3 2142.47  4595.4  2138.8
  4622.8 2135.19    4630 2133.02  4654.2 2131.66    4716 2131.46  4784.3 2129.47
  4809.3 2129.97  4923.2 2127.48  4938.5 2126.15  4954.3 2119.77  4989.5 2117.39
  4990.1 2116.89  5022.3 2117.39  5022.4 2118.57  5027.5 2119.44  5036.4 2123.19
  5046.6 2129.14  5066.9 2137.65  5075.8 2140.93  5087.2 2143.13  5107.5 2143.37
  5158.4 2139.74    5199 2138.61  5304.5 2139.49  5474.7 2152.43  5554.8 2159.51
#Mann= 5 ,-1 , 0
  4293.7     .07       0  4468.5      .1       0  4654.2     .07       0
  4989.5     .05       0  5022.3     .07       0
Bank Sta=4989.5,5022.3
XS Rating Curve= 0 ,0
Exp/Cntr=0.3,0.1

Type RM Length L Ch R = 1 ,124051  ,539,539,539
BEGIN DESCRIPTION:
South Fork Guadalupe River 193.0
END DESCRIPTION:
XS GIS Cut Line= 3
      1806025.01     13891324.98        1806225.       13890525.
      1806574.99     13890325.01
#Sta/Elev= 30
  4179.5 2151.64  4238.7  2148.9  4334.1 2142.94  4540.2 2134.62  4651.1 2133.43
  4705.2 2132.12  4787.6 2127.71  4797.9 2127.61    4816 2129.39  4849.5 2128.57
  4880.4 2126.53  4898.4 2121.73  4903.6 2121.05  4944.8 2117.18  4964.5 2116.64
  4965.1 2116.14  4996.8 2116.14  4997.4 2116.64  5001.5 2123.14    5007 2123.14
    5012 2124.38  5017.8 2129.77  5033.6 2131.01  5039.4 2134.35  5055.2 2136.55
    5120 2142.69  5135.8  2143.2    5179 2146.58  5216.5 2148.51  5407.2 2161.29
#Mann= 3 ,-1 , 0
  4179.5     .07       0  4964.5     .05       0  4997.4     .07       0
Bank Sta=4964.5,4997.4
XS Rating Curve= 0 ,0
Exp/Cntr=0.3,0.1

Type RM Length L Ch R = 1 ,123512  ,528,528,528
BEGIN DESCRIPTION:
South Fork Guadalupe River 192.0
END DESCRIPTION:
XS GIS Cut Line= 3
        1806625.       13891525.        1806675.       13890775.
        1806675.     13890374.97
#Sta/Elev= 30
  4243.6 2167.87  4293.7 2165.51  4353.8 2155.15  4383.9 2151.47    4444 2142.07
  4514.2 2135.89  4584.4 2134.37  4674.6 2135.34  4764.8 2134.19  4794.8 2132.56
  4834.9 2126.24  4844.9 2125.41  4905.1 2121.74  4945.2 2121.48  4965.2 2118.75
  5005.3 2116.71  5008.8 2115.67  5009.4 2115.17  5041.2 2115.17  5041.7 2115.67
  5045.3 2118.53  5055.3 2120.25  5105.3 2139.92  5115.3 2143.07  5135.3 2147.29
  5175.3 2150.61  5215.3  2151.8  5295.3 2155.75  5365.3 2161.27  5395.3 2162.08
#Mann= 3 ,-1 , 0
  4243.6     .07       0  5008.8     .05       0  5041.7     .07       0
Bank Sta=5008.8,5041.7
XS Rating Curve= 0 ,0
Exp/Cntr=0.3,0.1

Type RM Length L Ch R = 1 ,122984  ,592,592,592
BEGIN DESCRIPTION:
South Fork Guadalupe River 191.0
END DESCRIPTION:
XS GIS Cut Line= 3
      1806874.98     13891575.04        1807075.       13891075.
        1807125.     13890674.98
#Sta/Elev= 30
  4449.9 2168.14  4482.3 2166.46  4513.2 2163.19  4542.8 2156.37    4590 2150.09
  4626.3 2143.86    4633 2141.73  4704.4 2133.89  4740.7 2132.11  4758.2 2129.35
  4773.1 2129.08  4782.5 2131.21  4812.1 2131.91  4848.5 2126.98  4919.8 2124.59
    4944 2121.91  4956.2 2118.23  4966.9 2117.07    4979 2117.97  5009.8 2115.67
  5010.4 2115.17  5042.8 2115.67  5048.9 2116.85  5089.2 2118.02  5099.3 2119.38
  5119.5 2126.16  5149.7 2133.53  5210.2 2141.42  5280.7 2146.58  5391.6 2150.38
#Mann= 3 ,-1 , 0
  4449.9     .07       0  5009.8     .05       0  5042.8     .07       0
Bank Sta=5009.8,5042.8
XS Rating Curve= 0 ,0
Exp/Cntr=0.3,0.1

Type RM Length L Ch R = 1 ,122392  ,571,571,571
BEGIN DESCRIPTION:
South Fork Guadalupe River 190.0
END DESCRIPTION:
XS GIS Cut Line= 3
        1807675.     13891725.01        1807525.       13891325.
      1807525.68     13890651.51
#Sta/Elev= 30
  4572.9 2170.54  4630.3  2164.4    4637 2163.55  4643.2 2161.49  4668.1 2157.08
  4722.4 2145.67  4728.7 2141.83    4734 2140.79  4743.8 2137.35  4753.6 2132.87
  4758.9 2132.22  4765.2 2128.47  4783.8 2122.02  4789.2 2122.43  4797.2  2120.8
  4807.9 2120.44  4829.2 2120.97  4867.2 2119.37  4960.1 2116.17  5010.1 2116.54
  5013.6    2116  5014.2  2115.5  5046.7    2116  5070.1    2118  5130.1 2124.88
  5150.1 2128.51  5250.1 2135.46  5360.1  2140.8  5510.1  2146.6  5673.6 2151.66
#Mann= 5 ,-1 , 0
  4572.9     .07       0  4630.3      .1       0  4867.2     .07       0
  5013.6     .05       0  5046.7     .07       0
Bank Sta=5013.6,5046.7
XS Rating Curve= 0 ,0
Exp/Cntr=0.3,0.1

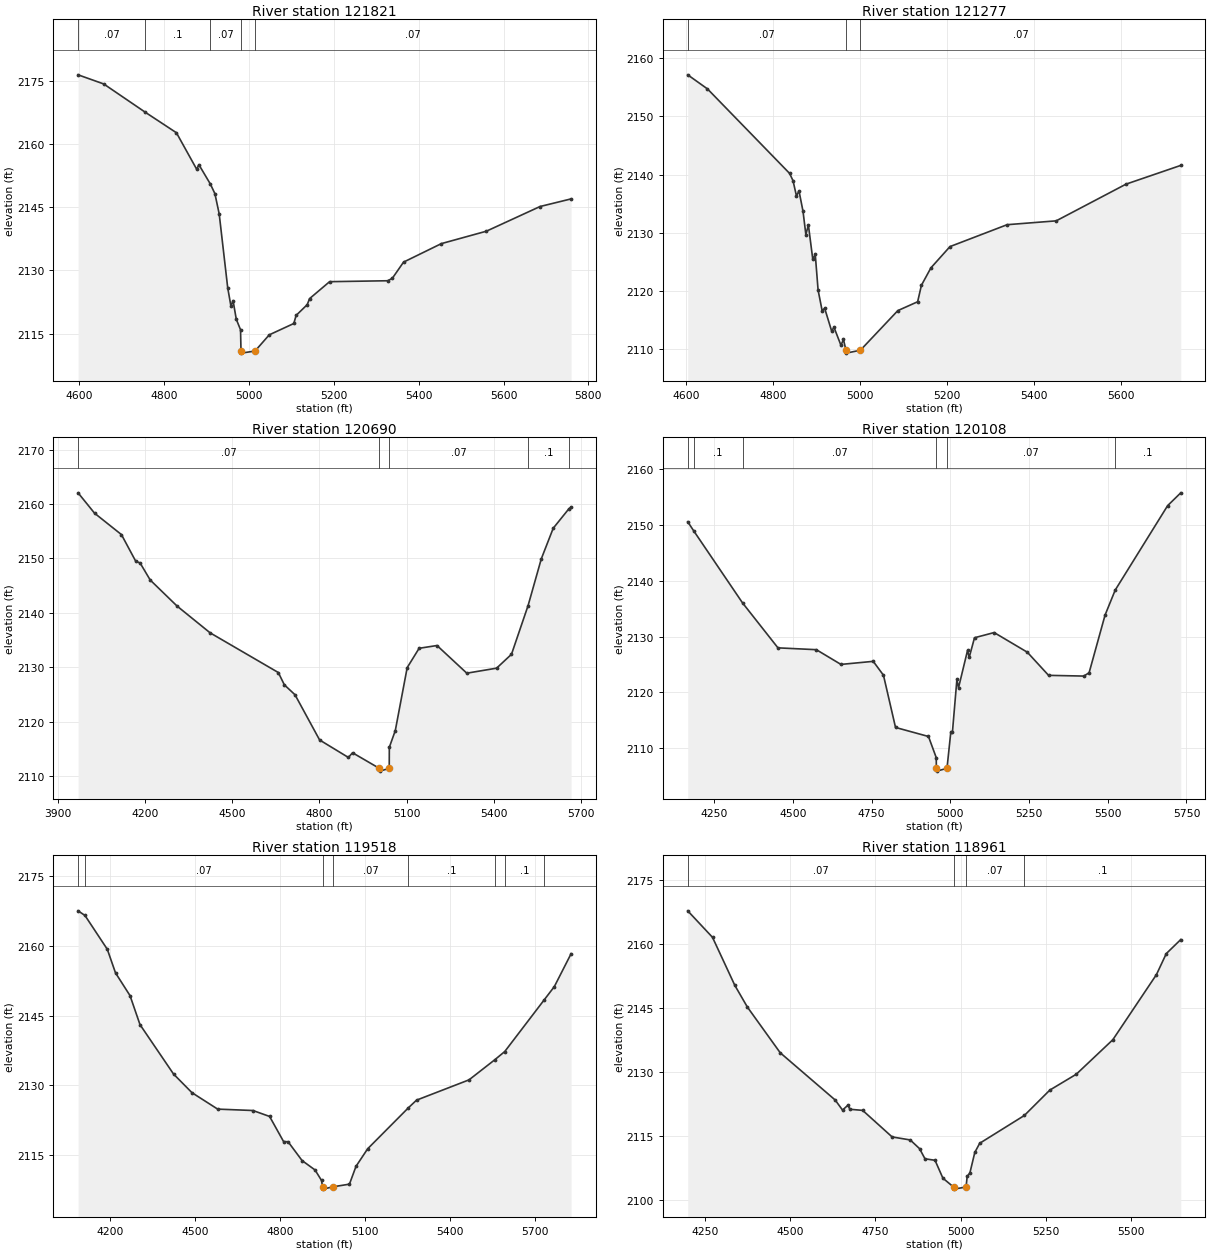
Type RM Length L Ch R = 1 ,121821  ,544,544,544
BEGIN DESCRIPTION:
South Fork Guadalupe River 189.0
END DESCRIPTION:
XS GIS Cut Line= 3
        1807975.     13891824.98        1808025.       13891425.
      1807785.46     13890704.89
#Sta/Elev= 30
  4597.3 2176.41  4657.7 2174.25  4755.9 2167.52  4829.1 2162.67  4876.9    2154
    4882  2155.1    4909 2150.52  4919.8 2148.22  4929.9 2143.42    4950 2125.87
  4957.6 2121.53  4962.6 2122.84  4970.2 2118.42  4980.2 2115.94  4981.3 2110.89
  4981.9 2110.39  5014.4 2110.89  5047.9 2114.73  5105.8 2117.42  5111.2 2119.34
  5137.4 2121.89  5142.8 2123.31  5190.1 2127.34  5327.1 2127.56    5338 2128.15
  5364.4 2131.98  5453.6 2136.37  5559.5 2139.31  5686.1 2145.17  5759.3 2146.98
#Mann= 5 ,-1 , 0
  4597.3     .07       0  4755.9      .1       0    4909     .07       0
  4981.3     .05       0  5014.4     .07       0
Bank Sta=4981.3,5014.4
XS Rating Curve= 0 ,0
Exp/Cntr=0.3,0.1

Type RM Length L Ch R = 1 ,121277  ,587,587,587
BEGIN DESCRIPTION:
South Fork Guadalupe River 188.0
END DESCRIPTION:
XS GIS Cut Line= 3
      1808324.98     13891625.03        1808525.       13891275.
      1808178.07     13890633.22
#Sta/Elev= 30
  4604.6 2157.15    4650 2154.73  4838.6 2140.23  4846.5 2138.98  4854.4 2136.35
  4860.2 2137.23  4869.5 2133.71    4876 2129.72  4881.8 2131.37  4891.9 2125.48
  4897.6 2126.32  4904.1  2120.2  4913.4 2116.66  4919.2 2117.07    4935 2113.22
  4940.8 2113.77  4956.6 2110.72  4962.4 2111.71  4968.1 2109.87  4968.7 2109.37
  5001.3 2109.87  5087.3 2116.67  5132.8 2118.19  5141.5 2121.02  5163.3 2124.01
  5207.1 2127.66  5338.4 2131.42  5451.1 2132.08  5611.5 2138.38  5737.3  2141.6
#Mann= 3 ,-1 , 0
  4604.6     .07       0  4968.1     .05       0  5001.3     .07       0
Bank Sta=4968.1,5001.3
XS Rating Curve= 0 ,0
Exp/Cntr=0.3,0.1

Type RM Length L Ch R = 1 ,120690  ,582,582,582
BEGIN DESCRIPTION:
South Fork Guadalupe River 187.0
END DESCRIPTION:
XS GIS Cut Line= 3
      1808424.99     13891975.02        1809075.       13891175.
        1809225.     13890524.98
#Sta/Elev= 30
  3968.8 2162.05  4025.6 2158.31  4118.2 2154.38  4167.8 2149.45  4182.2 2149.19
  4217.3 2146.04    4310 2141.25  4423.5 2136.35  4658.4 2129.06  4679.2  2126.8
  4715.9 2124.98  4800.6 2116.68  4899.7 2113.47  4914.1 2114.33  5006.6 2111.46
  5007.3 2110.96  5040.4 2111.46  5040.7 2115.34  5061.2 2118.39  5102.2 2129.96
  5143.3 2133.51  5204.9 2134.02  5307.5 2128.94  5410.1 2129.86  5461.4 2132.41
  5518.6 2141.36  5564.1 2149.94  5605.1 2155.55  5659.2 2159.13  5666.7 2159.42
#Mann= 5 ,-1 , 0
  3968.8     .07       0  5006.6     .05       0  5040.4     .07       0
  5518.6      .1       0  5659.2     .07       0
Bank Sta=5006.6,5040.4
XS Rating Curve= 0 ,0
Exp/Cntr=0.3,0.1

Type RM Length L Ch R = 1 ,120108  ,590,590,590
BEGIN DESCRIPTION:
South Fork Guadalupe River 186.0
END DESCRIPTION:
XS GIS Cut Line= 3
      1809374.99     13892075.02        1809625.       13891275.
        1809425.     13890574.98
#Sta/Elev= 30
  4165.7 2150.58    4185 2148.93  4339.8 2136.04  4452.3 2127.98  4574.3 2127.65
  4652.4 2125.01    4755 2125.56  4787.5 2123.07  4825.8 2113.71  4930.5 2112.09
  4955.2 2108.29  4955.5 2106.38  4956.2 2105.88  4989.3 2106.38  5001.3 2112.82
  5006.5 2112.82  5020.8 2122.32    5026 2120.84  5054.6 2127.53  5059.8 2126.26
  5076.7 2129.79  5139.1 2130.72  5244.4  2127.2    5312 2123.05  5423.8 2122.92
  5440.7 2123.51  5491.4 2133.85  5523.7 2138.34  5690.3 2153.48  5731.9 2155.77
#Mann= 6 ,-1 , 0
  4165.7     .07       0    4185      .1       0  4339.8     .07       0
  4955.5     .05       0  4989.3     .07       0  5523.7      .1       0
Bank Sta=4955.5,4989.3
XS Rating Curve= 0 ,0
Exp/Cntr=0.3,0.1

Type RM Length L Ch R = 1 ,119518  ,557,557,557
BEGIN DESCRIPTION:
South Fork Guadalupe River 185.0
END DESCRIPTION:
XS GIS Cut Line= 3
        1809625.       13892425.        1810075.       13891625.
        1810875.       13891425.
#Sta/Elev= 30
  4086.1 2167.58  4110.5 2166.58  4189.4  2159.3  4218.4 2154.22  4269.7 2149.32
    4305 2143.07  4423.6 2132.43  4488.6 2128.42  4579.5 2124.88  4704.1 2124.58
    4763  2123.3  4812.4 2117.89  4828.4 2117.85  4877.8  2113.8  4923.7 2111.77
  4946.6 2109.51  4950.2 2108.15  4951.1 2107.65    4987 2108.15  5045.2 2108.72
  5068.4 2112.56  5109.6 2116.34  5253.8 2125.18  5282.3 2126.81  5467.8 2131.18
  5558.7  2135.5  5594.1 2137.28  5733.4  2148.4  5769.3 2151.26  5828.6 2158.35
#Mann= 8 ,-1 , 0
  4086.1    .035       0  4110.5     .07       0  4950.2     .05       0
    4987     .07       0  5253.8      .1       0  5558.7     .07       0
  5594.1      .1       0  5733.4     .07       0
Bank Sta=4950.2,4987
XS Rating Curve= 0 ,0
Exp/Cntr=0.3,0.1

Type RM Length L Ch R = 1 ,118961  ,484,484,484
BEGIN DESCRIPTION:
South Fork Guadalupe River 184.0
END DESCRIPTION:
XS GIS Cut Line= 3
      1810024.99     13892725.02        1810425.       13892025.
      1810925.03     13891624.98
#Sta/Elev= 30
  4199.5 2167.82  4272.2  2161.6  4337.7 2150.33  4374.4 2145.25  4470.9 2134.51
  4632.2 2123.42  4653.7 2121.06  4669.6 2122.21  4675.3 2121.25  4712.8 2120.99
  4799.2 2114.76  4852.4 2114.05  4879.8    2112  4895.6 2109.63  4925.1 2109.28
  4948.2 2105.08  4979.4 2103.01  4980.3 2102.51  5016.2 2103.01  5019.4 2105.49
  5027.4 2106.31  5041.8 2111.12  5056.2 2113.27  5187.1 2119.79  5261.9 2125.75
  5339.5 2129.47  5446.8 2137.57  5574.8 2152.86  5603.6 2157.78  5646.1 2161.08
#Mann= 4 ,-1 , 0
  4199.5     .07       0  4979.4     .05       0  5016.2     .07       0
  5187.1      .1       0
Bank Sta=4979.4,5016.2
XS Rating Curve= 0 ,0
Exp/Cntr=0.3,0.1

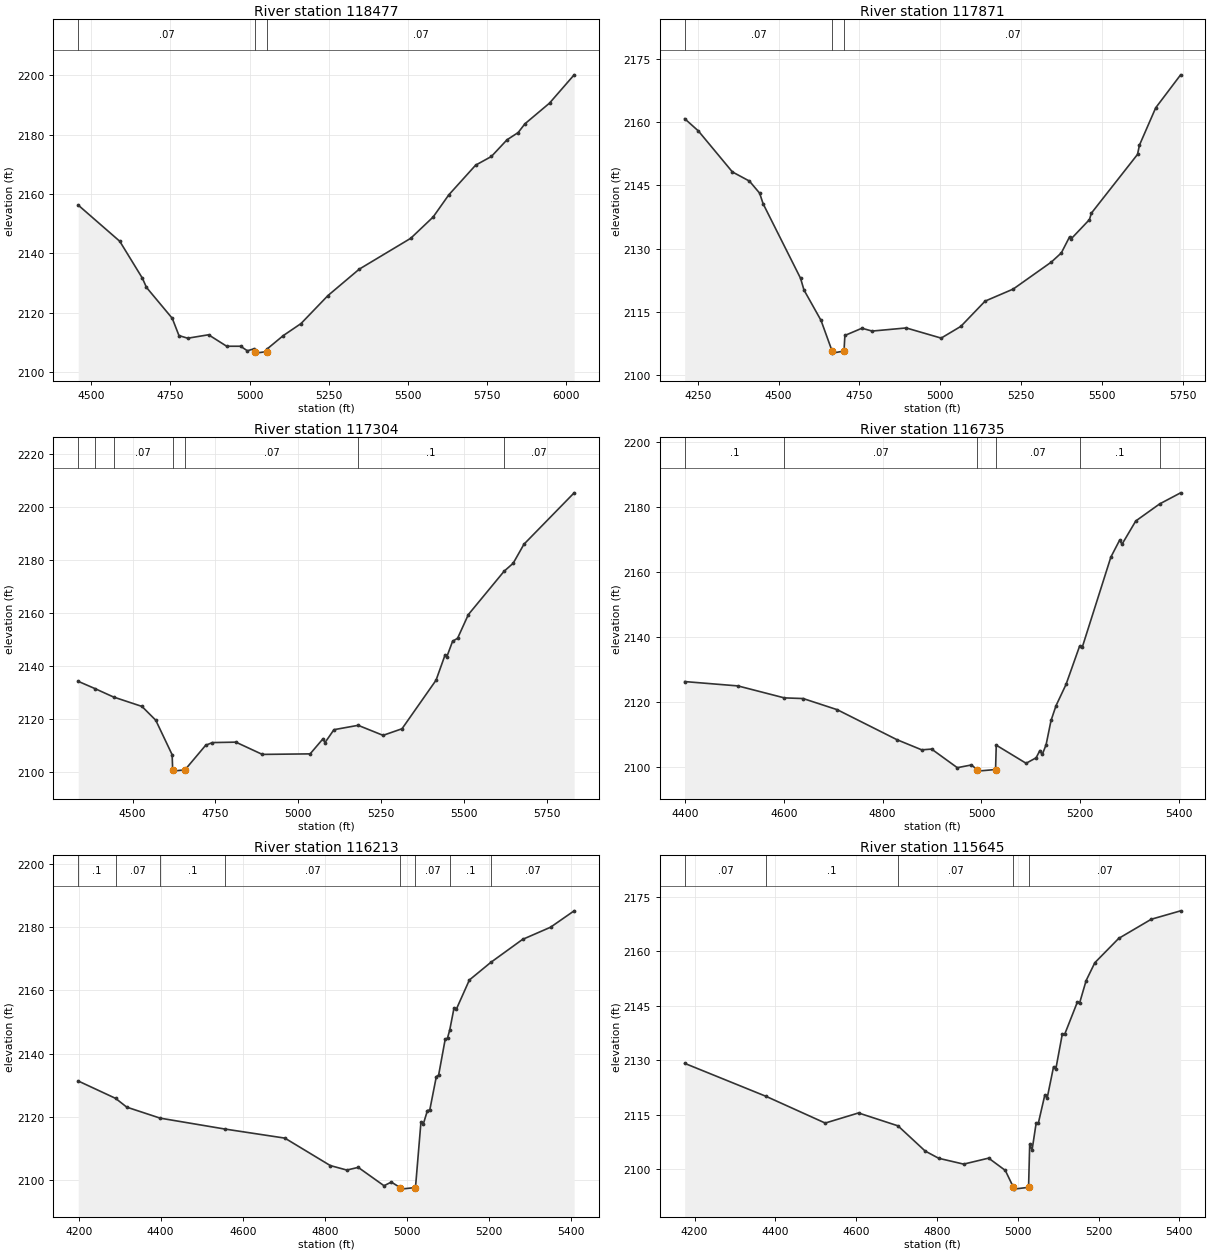
Type RM Length L Ch R = 1 ,118477  ,606,606,606
BEGIN DESCRIPTION:
South Fork Guadalupe River 183.0
END DESCRIPTION:
XS GIS Cut Line= 3
      1810425.02     13892824.98      1810711.34     13892385.72
      1811424.99     13891625.01
#Sta/Elev= 30
  4458.5 2156.25  4589.8 2144.08  4661.4 2131.63  4674.2 2128.55  4755.8 2118.13
  4776.9 2112.33  4804.6 2111.44  4870.4  2112.6  4927.7 2108.74  4971.8 2108.74
  4993.1 2107.21  5014.1 2107.87  5017.1 2106.92    5018 2106.42    5054 2106.92
  5056.6 2107.91  5106.4 2112.31  5162.6 2116.37  5247.6 2125.78  5346.7 2134.69
  5509.4 2145.08  5580.2 2152.24  5629.6 2159.69  5714.5  2169.7  5764.3 2172.62
  5813.7 2178.24  5848.9 2180.67  5870.3 2183.62    5948 2190.58  6025.9 2200.11
#Mann= 3 ,-1 , 0
  4458.5     .07       0  5017.1     .05       0    5054     .07       0
Bank Sta=5017.1,5054
XS Rating Curve= 0 ,0
Exp/Cntr=0.3,0.1

Type RM Length L Ch R = 1 ,117871  ,567,567,567
BEGIN DESCRIPTION:
South Fork Guadalupe River 182.0
END DESCRIPTION:
XS GIS Cut Line= 3
      1810424.97     13892925.01        1811175.       13892675.
        1811425.     13891975.01
#Sta/Elev= 30
  4209.4 2160.81  4251.6 2157.92    4357 2148.19  4409.7 2146.02  4441.3 2143.15
  4451.9 2140.66  4567.8 2122.98  4578.4  2120.2  4631.1    2113  4665.3 2105.74
  4666.2 2105.24  4702.2 2105.74  4704.9 2109.43  4757.6 2111.14  4789.2 2110.47
  4894.6 2111.21  5002.7  2108.8  5063.7 2111.59  5138.6 2117.57  5225.6 2120.43
  5343.5 2126.83  5374.3 2128.99  5399.8  2132.8  5405.1 2132.36  5461.4  2136.9
  5467.2 2138.41    5610 2152.35  5615.9 2154.53  5666.3  2163.4  5743.3 2171.21
#Mann= 3 ,-1 , 0
  4209.4     .07       0  4665.3     .05       0  4702.2     .07       0
Bank Sta=4665.3,4702.2
XS Rating Curve= 0 ,0
Exp/Cntr=0.3,0.1

Type RM Length L Ch R = 1 ,117304  ,569,569,569
BEGIN DESCRIPTION:
South Fork Guadalupe River 181.0
END DESCRIPTION:
XS GIS Cut Line= 3
      1810875.04     13893174.99        1811525.       13893075.
      1812325.04     13893325.01
#Sta/Elev= 30
  4336.2 2134.28  4386.3 2131.56  4442.8 2128.35  4528.4  2124.8  4570.1 2119.58
  4619.5 2106.55  4621.1 2100.85    4622 2100.35  4658.3 2100.85  4720.6 2110.12
  4740.9 2111.14  4811.7  2111.3  4891.4 2106.67  5035.7 2106.87    5075 2112.65
  5080.2 2111.08  5107.5 2116.01  5180.5 2117.66  5255.7 2113.87  5312.8 2116.36
  5415.5 2134.72  5442.7 2144.27    5448 2143.57  5465.3  2149.4  5480.5 2150.57
  5512.9  2159.5  5620.7 2175.88  5648.1  2178.9  5680.6 2186.09    5832 2205.51
#Mann= 7 ,-1 , 0
  4336.2     .07       0  4386.3      .1       0  4442.8     .07       0
  4621.1     .05       0  4658.3     .07       0  5180.5      .1       0
  5620.7     .07       0
Bank Sta=4621.1,4658.3
XS Rating Curve= 0 ,0
Exp/Cntr=0.3,0.1

Type RM Length L Ch R = 1 ,116735  ,522,522,522
BEGIN DESCRIPTION:
South Fork Guadalupe River 180.0
END DESCRIPTION:
XS GIS Cut Line= 3
      1811127.84     13893632.71        1811725.       13893575.
      1812125.04     13893625.01
#Sta/Elev= 30
  4399.7 2126.23  4507.4 2124.89  4601.2  2121.2  4639.4 2120.99  4708.3 2117.55
  4828.9 2108.31  4879.1 2105.17  4899.2  2105.4  4951.1 2099.66  4979.6  2100.5
    4991  2099.1  4991.9  2098.6  5028.5  2099.1  5029.9 2106.61  5090.3 2101.02
  5110.5 2102.71  5118.1 2104.95  5123.1 2103.76  5130.7 2106.74  5140.7 2114.22
  5150.8 2118.79    5171 2125.34  5198.3 2137.09  5203.7 2136.75  5261.7 2164.63
  5279.3 2169.82  5284.3 2168.61  5312.1 2175.78  5360.4 2181.04  5402.8 2184.46
#Mann= 6 ,-1 , 0
  4399.7      .1       0  4601.2     .07       0    4991     .05       0
  5028.5     .07       0  5198.3      .1       0  5360.4     .07       0
Bank Sta=4991,5028.5
XS Rating Curve= 0 ,0
Exp/Cntr=0.3,0.1

Type RM Length L Ch R = 1 ,116213  ,568,568,568
BEGIN DESCRIPTION:
South Fork Guadalupe River 179.0
END DESCRIPTION:
XS GIS Cut Line= 3
      1811075.01       13893925.        1811875.       13894025.
      1812224.98     13893825.01
#Sta/Elev= 30
  4198.9 2131.34  4290.1 2125.85  4317.3 2123.08  4398.6 2119.61  4555.9 2116.18
  4702.8  2113.3  4813.6 2104.63  4853.9 2103.21  4881.7 2104.06  4944.6 2098.26
  4962.3 2099.42  4983.8 2097.69  4984.8 2097.19  5021.3 2097.69  5034.6  2118.3
  5040.4 2117.76  5050.5 2122.02  5056.2 2122.21  5072.1 2132.71  5077.8 2133.24
  5093.7 2144.48  5099.4 2144.91  5104.9 2147.49  5115.3 2154.41    5121 2154.03
  5152.7 2163.24  5204.9 2168.79  5282.3 2176.05  5350.6  2179.9  5408.2 2185.08
#Mann= 8 ,-1 , 0
  4198.9      .1       0  4290.1     .07       0  4398.6      .1       0
  4555.9     .07       0  4983.8     .05       0  5021.3     .07       0
  5104.9      .1       0  5204.9     .07       0
Bank Sta=4983.8,5021.3
XS Rating Curve= 0 ,0
Exp/Cntr=0.3,0.1

Type RM Length L Ch R = 1 ,115645  ,548,548,548
BEGIN DESCRIPTION:
South Fork Guadalupe River 178.0
END DESCRIPTION:
XS GIS Cut Line= 3
      1811025.01       13894375.        1811825.       13894575.
      1812174.98     13894375.01
#Sta/Elev= 30
  4175.4 2129.18  4376.9  2120.1  4523.3 2112.75  4605.7 2115.53  4703.5 2111.98
  4770.7 2105.05  4804.2 2103.06    4866 2101.45  4927.9  2103.1  4969.1 2099.72
  4989.2 2095.07  4990.1 2094.57  5026.7 2095.07  5029.5 2106.96  5035.3 2105.27
  5045.4 2112.69  5051.1 2112.82    5067 2120.51  5072.7 2119.61  5088.6 2128.26
  5094.3 2127.71  5110.2 2137.23  5115.9 2137.12  5147.6 2146.07  5153.3 2145.88
  5169.2 2151.96  5190.8 2156.88  5249.8 2163.56  5330.4 2168.83  5403.1 2171.15
#Mann= 5 ,-1 , 0
  4175.4     .07       0  4376.9      .1       0  4703.5     .07       0
  4989.2     .05       0  5026.7     .07       0
Bank Sta=4989.2,5026.7
XS Rating Curve= 0 ,0
Exp/Cntr=0.3,0.1

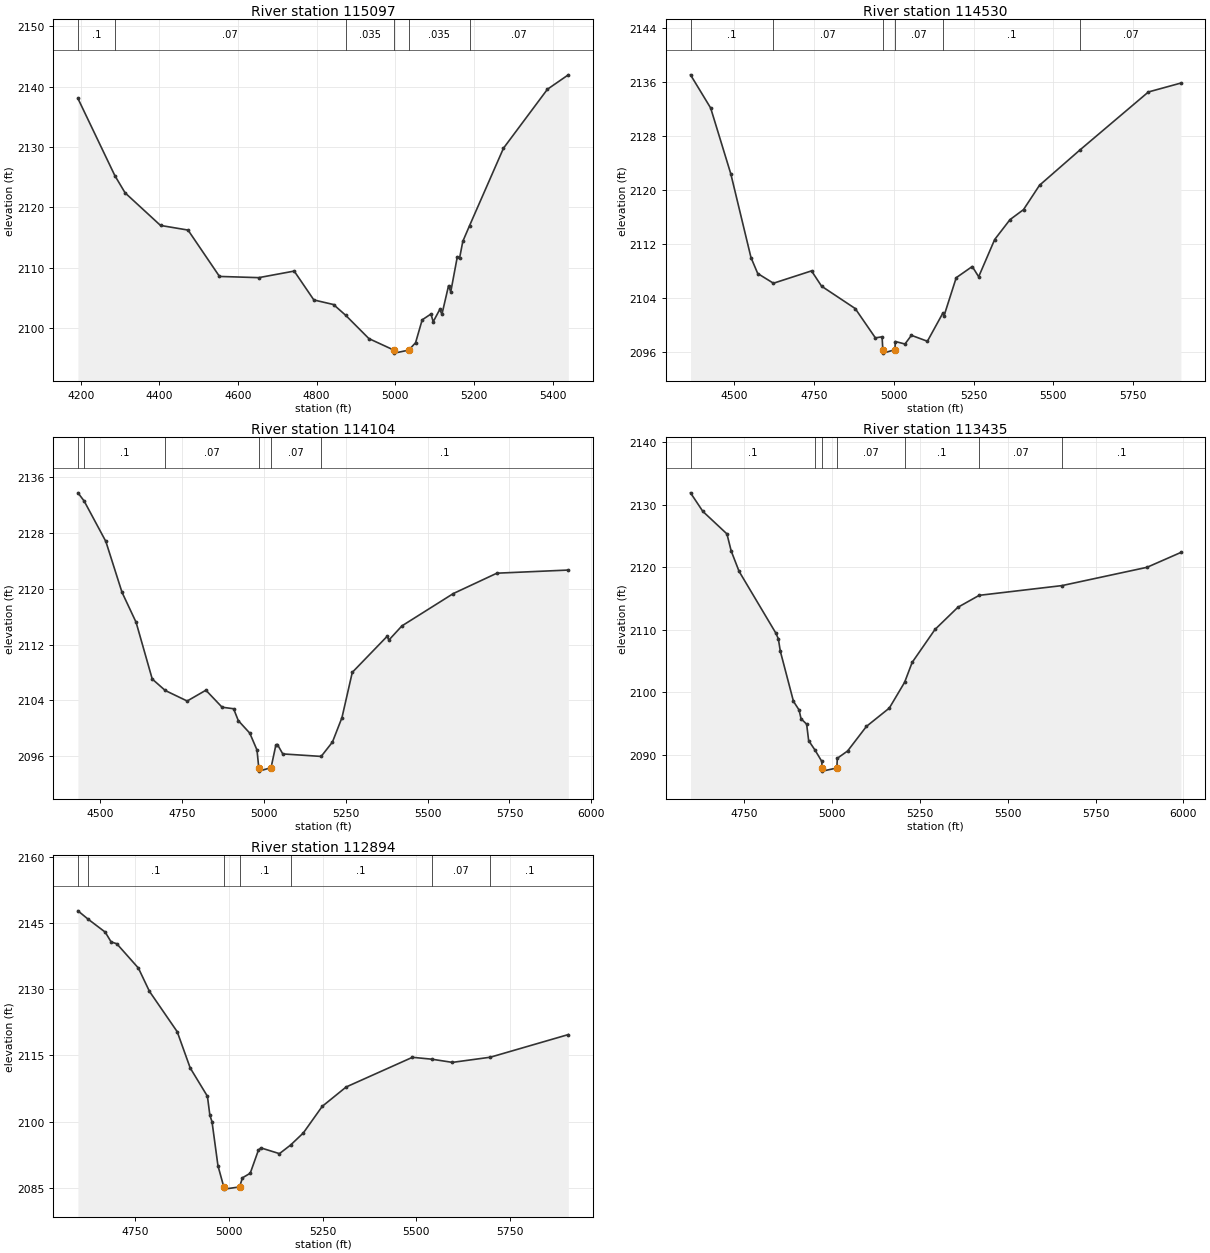
Type RM Length L Ch R = 1 ,115097  ,567,567,567
BEGIN DESCRIPTION:
South Fork Guadalupe River 177.0
END DESCRIPTION:
XS GIS Cut Line= 3
      1810874.97       13895075.        1811675.       13895075.
      1812074.96     13894875.02
#Sta/Elev= 30
  4192.8 2138.05  4286.7 2125.25  4312.8 2122.39  4402.8 2116.99  4472.8 2116.22
  4552.8 2108.53  4652.8 2108.33  4742.8 2109.42  4792.8 2104.63  4842.8 2103.87
  4873.7 2102.09  4932.8 2098.22  4996.4 2096.31  4997.4 2095.81    5034 2096.31
  5051.5 2097.53  5068.3 2101.33  5090.7  2102.3  5096.3 2101.01    5113 2103.05
  5118.6 2102.26  5135.4    2107    5141 2105.97  5157.7 2111.81  5163.3 2111.52
  5171.7 2114.36  5188.9 2116.97  5275.1  2129.8  5386.9 2139.58    5440 2141.97
#Mann= 6 ,-1 , 0
  4192.8      .1       0  4286.7     .07       0  4873.7    .035       0
  4996.4    .035       0    5034    .035       0  5188.9     .07       0
Bank Sta=4996.4,5034
XS Rating Curve= 0 ,0
Exp/Cntr=0.3,0.1

Type RM Length L Ch R = 1 ,114530  ,426,426,426
BEGIN DESCRIPTION:
South Fork Guadalupe River 176.0
END DESCRIPTION:
XS GIS Cut Line= 3
        1810875.       13895375.        1811475.       13895575.
      1812376.44     13895489.93
#Sta/Elev= 30
  4362.2 2137.08  4425.4 2132.16  4488.7 2122.38  4551.9 2109.99    4573 2107.63
  4622.3 2106.19  4741.7 2108.02  4773.3 2105.75  4878.7 2102.44    4942 2098.09
    4963 2098.25  4965.3 2096.33  4966.3 2095.83  5002.9 2096.33  5004.7 2097.55
  5034.8 2097.18  5054.9 2098.47  5105.1 2097.59  5153.8 2101.78  5157.4 2101.38
  5195.5 2107.01  5245.8 2108.67  5265.9 2107.15  5316.1 2112.67  5364.2 2115.62
  5406.5  2117.1  5456.7 2120.71  5583.9 2125.96  5798.2 2134.54  5900.1 2135.86
#Mann= 6 ,-1 , 0
  4362.2      .1       0  4622.3     .07       0  4965.3     .05       0
  5002.9     .07       0  5153.8      .1       0  5583.9     .07       0
Bank Sta=4965.3,5002.9
XS Rating Curve= 0 ,0
Exp/Cntr=0.3,0.1

Type RM Length L Ch R = 1 ,114104  ,669,669,669
BEGIN DESCRIPTION:
South Fork Guadalupe River 175.0
END DESCRIPTION:
XS GIS Cut Line= 3
      1810875.01     13895475.01      1811244.17      13895914.9
      1812157.54     13896052.17
#Sta/Elev= 30
  4431.9 2133.78  4450.8 2132.61  4517.1 2126.81  4566.5 2119.51  4609.5 2115.21
  4658.9 2107.06  4698.6 2105.42  4765.6 2103.91  4822.8 2105.46  4872.2 2103.02
  4907.4  2102.8  4921.7  2101.1  4956.8  2099.3  4978.9 2096.87  4984.2 2094.35
  4985.1 2093.85  5021.8 2094.35  5036.4 2097.57  5041.4 2097.66  5057.6 2096.32
  5174.9 2095.96  5209.3 2098.02  5238.4 2101.53  5269.9 2108.02  5376.5  2113.2
  5381.6 2112.65  5421.6 2114.69  5578.6 2119.33  5711.6 2122.25  5929.8  2122.7
#Mann= 6 ,-1 , 0
  4431.9     .07       0  4450.8      .1       0  4698.6     .07       0
  4984.2     .05       0  5021.8     .07       0  5174.9      .1       0
Bank Sta=4984.2,5021.8
XS Rating Curve= 0 ,0
Exp/Cntr=0.3,0.1

Type RM Length L Ch R = 1 ,113435  ,541,541,541
BEGIN DESCRIPTION:
South Fork Guadalupe River 174.0
END DESCRIPTION:
XS GIS Cut Line= 3
      1811075.02     13896874.97        1811275.       13896525.
      1812190.83     13896143.74
#Sta/Elev= 30
  4597.6 2131.93  4632.8 2128.95  4701.2 2125.35  4713.5 2122.59  4735.8 2119.35
  4839.4 2109.55  4847.4 2108.57  4853.1 2106.56  4890.5 2098.53  4906.4 2097.15
  4912.1 2095.74    4928 2094.87  4933.7 2092.24  4951.8 2090.72  4971.2  2088.9
  4971.7 2087.85  4972.7 2087.35  5013.8 2087.85  5015.3 2089.41  5044.6 2090.58
  5098.2 2094.52  5163.2 2097.45  5206.8 2101.59  5228.1 2104.76  5293.1 2110.04
  5358.1 2113.59  5418.9 2115.51  5654.4 2117.07  5896.3    2120  5992.7 2122.38
#Mann= 7 ,-1 , 0
  4597.6      .1       0  4951.8     .07       0  4971.7     .05       0
  5013.8     .07       0  5206.8      .1       0  5418.9     .07       0
  5654.4      .1       0
Bank Sta=4971.7,5013.8
XS Rating Curve= 0 ,0
Exp/Cntr=0.3,0.1

Type RM Length L Ch R = 1 ,112894  ,560,560,560
BEGIN DESCRIPTION:
South Fork Guadalupe River 173.0
END DESCRIPTION:
XS GIS Cut Line= 3
      1811174.98     13897175.01        1811525.       13896975.
      1812216.45     13896390.55
#Sta/Elev= 30
  4596.9 2147.77  4623.6 2145.91  4669.6 2142.95  4685.5 2140.72  4700.6 2140.31
  4758.2  2134.8  4787.7 2129.53  4861.8 2120.38  4896.4 2112.18  4942.4 2105.75
  4948.9 2101.48  4954.7 2099.96  4970.5 2090.02  4986.1 2085.21  4987.1 2084.71
  5028.2 2085.21  5035.8 2087.27  5056.6 2088.31  5078.6 2093.57  5085.2 2094.05
  5134.6 2092.75  5164.3  2094.7  5198.3 2097.44  5248.8 2103.47  5312.7 2107.86
  5489.5 2114.58  5541.2 2114.15  5596.1 2113.43  5697.2  2114.6  5905.4 2119.73
#Mann= 7 ,-1 , 0
  4596.9    .035       0  4623.6      .1       0  4986.1     .05       0
  5028.2      .1       0  5164.3      .1       0  5541.2     .07       0
  5697.2      .1       0
Bank Sta=4986.1,5028.2
XS Rating Curve= 0 ,0
Exp/Cntr=0.3,0.1