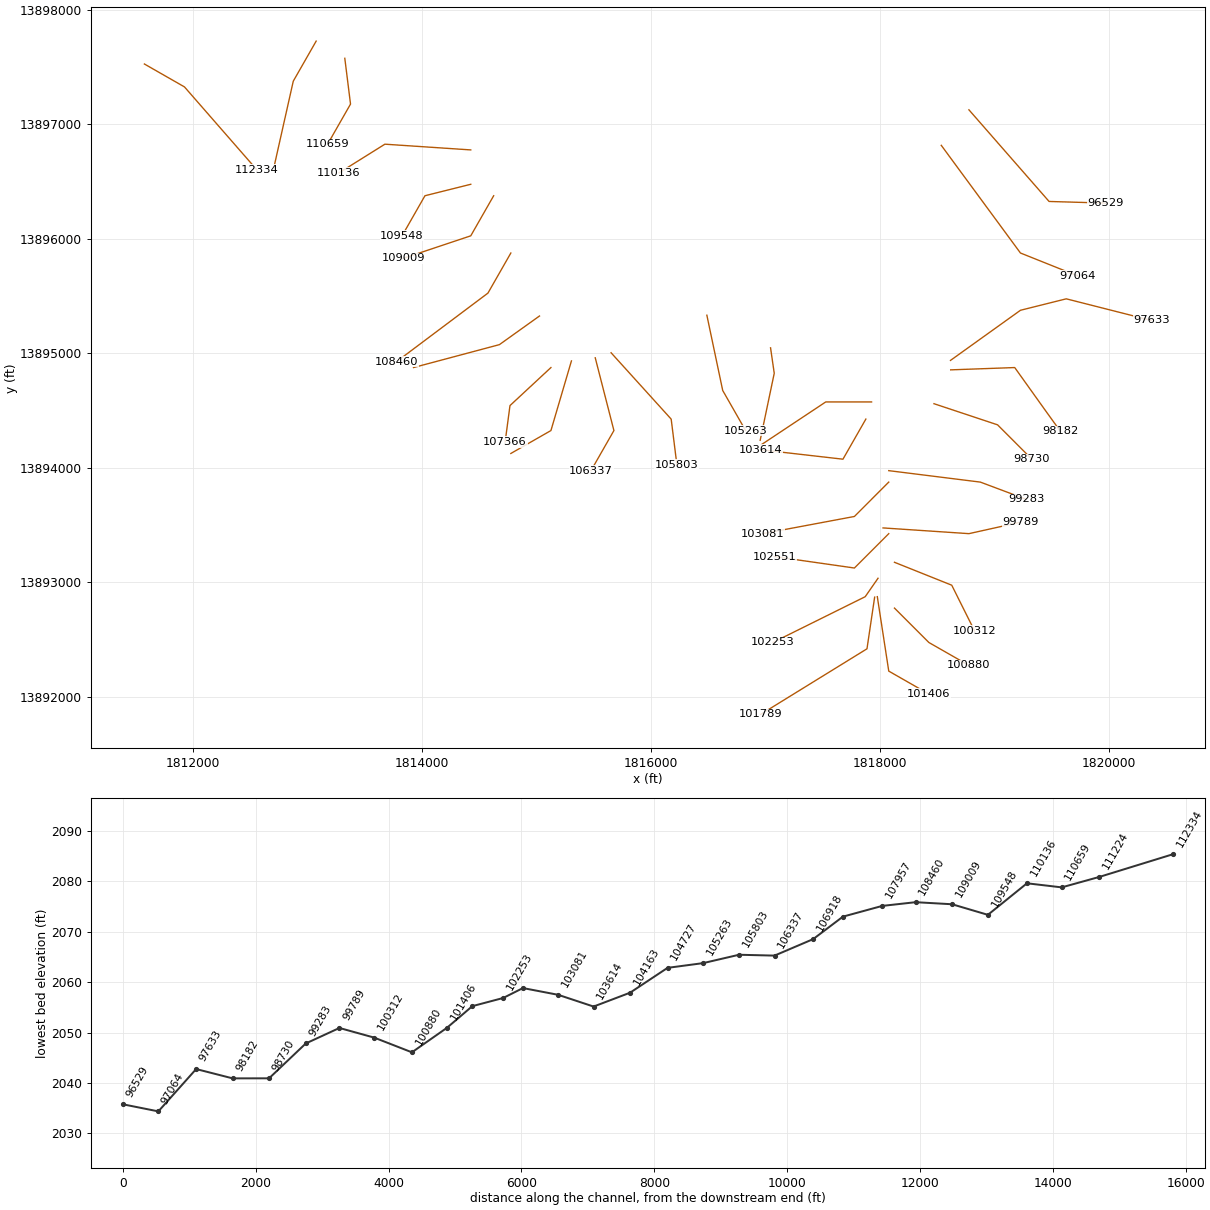
HEC-RAS study South Fork Guadalupe River.prj: South Fork Guadalupe River Base Level Engineering

--- South Fork Guadalupe River.g01 (geometry) --- (continued)

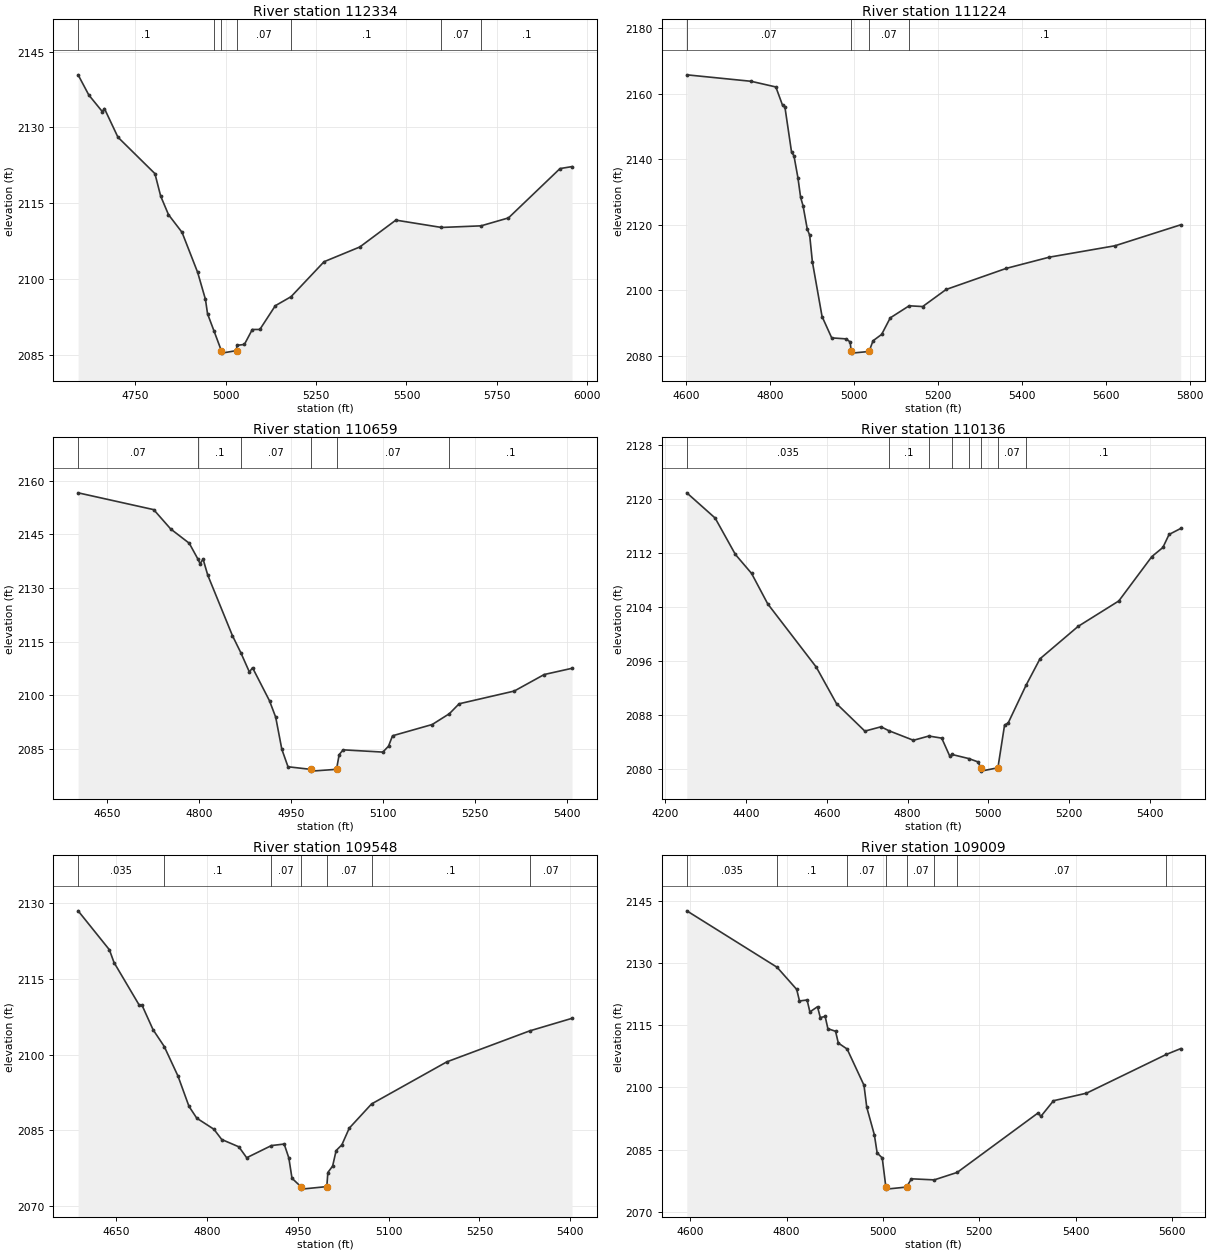
Type RM Length L Ch R = 1 ,112334  ,1110,1110,1110
BEGIN DESCRIPTION:
South Fork Guadalupe River 172.0
END DESCRIPTION:
XS GIS Cut Line= 3
      1811575.02     13897524.99        1811925.       13897325.
      1812557.76     13896600.38
#Sta/Elev= 30
  4592.4 2140.41  4621.9 2136.43  4659.3 2133.14  4665.1 2133.75  4702.5 2128.08
  4804.7 2120.88  4820.6 2116.44  4842.2 2112.77  4879.6 2109.28  4922.8 2101.36
  4944.4 2096.01  4950.1 2093.18  4968.2 2089.74  4988.2  2085.9  4989.2  2085.4
  5030.3  2085.9  5031.1 2086.93    5052 2087.12  5073.8 2090.07  5094.7 2090.08
  5137.4 2094.77    5181 2096.56  5272.2 2103.47  5370.9 2106.38  5470.6 2111.69
  5596.7 2110.24  5706.1 2110.56  5781.9 2112.13  5924.3 2121.88  5957.5 2122.27
#Mann= 7 ,-1 , 0
  4592.4      .1       0  4968.2     .07       0  4988.2     .05       0
  5030.3     .07       0    5181      .1       0  5596.7     .07       0
  5706.1      .1       0
Bank Sta=4988.2,5030.3
XS Rating Curve= 0 ,0
Exp/Cntr=0.3,0.1

Type RM Length L Ch R = 1 ,111224  ,565,565,565
BEGIN DESCRIPTION:
South Fork Guadalupe River 171.0
END DESCRIPTION:
XS GIS Cut Line= 3
      1813074.99     13897724.98        1812875.       13897375.
      1812705.19     13896619.24
#Sta/Elev= 30
  4600.9 2165.73  4754.2 2163.76  4813.2 2162.03  4829.1 2156.48  4834.8 2155.94
  4850.7 2142.13  4856.4 2141.04  4865.8 2134.39  4872.3 2128.37    4878 2125.84
  4888.1 2118.72  4893.9 2116.82  4900.3 2108.74  4923.4 2092.05  4946.4 2085.54
    4981 2085.23  4990.3 2084.29    4993 2081.39    4994 2080.89  5035.4 2081.39
    5045 2084.66  5065.5  2086.6    5086 2091.64  5131.1 2095.32  5163.3 2095.09
  5219.2 2100.29  5362.7 2106.73  5465.2 2110.14  5621.9 2113.62  5778.6 2120.01
#Mann= 4 ,-1 , 0
  4600.9     .07       0    4993     .05       0  5035.4     .07       0
  5131.1      .1       0
Bank Sta=4993,5035.4
XS Rating Curve= 0 ,0
Exp/Cntr=0.3,0.1

Type RM Length L Ch R = 1 ,110659  ,523,523,523
BEGIN DESCRIPTION:
South Fork Guadalupe River 170.0
END DESCRIPTION:
XS GIS Cut Line= 3
        1813325.     13897574.96        1813375.       13897175.
      1813174.99     13896824.99
#Sta/Elev= 30
  4602.3  2156.6  4725.7  2151.9  4753.4  2146.5  4783.7 2142.51  4798.1 2138.01
  4801.3 2136.79  4806.3 2138.07  4813.9  2133.6  4854.2 2116.68  4867.8 2111.95
  4881.9 2106.51    4887 2107.73  4914.7 2098.48  4924.8  2093.9  4934.8 2084.95
  4944.9 2080.04  4981.7 2079.32  4982.7 2078.82  5024.1 2079.32  5028.4 2083.43
  5034.9 2084.77  5099.7 2084.14    5109  2085.8  5115.5  2088.7  5180.3 2091.85
  5208.3 2094.87  5224.2 2097.64  5314.2  2101.2  5363.1 2105.82  5408.5 2107.56
#Mann= 6 ,-1 , 0
  4602.3     .07       0  4798.1      .1       0  4867.8     .07       0
  4981.7     .05       0  5024.1     .07       0  5208.3      .1       0
Bank Sta=4981.7,5024.1
XS Rating Curve= 0 ,0
Exp/Cntr=0.3,0.1

Type RM Length L Ch R = 1 ,110136  ,588,588,588
BEGIN DESCRIPTION:
South Fork Guadalupe River 169.0
END DESCRIPTION:
XS GIS Cut Line= 3
      1814425.03       13896775.        1813675.       13896825.
      1813274.99       13896575.
#Sta/Elev= 30
  4253.2 2120.87  4323.4 2117.13  4373.5 2111.74  4413.6 2108.93  4453.7 2104.41
  4573.9 2095.04    4624 2089.63  4694.2 2085.56  4734.3  2086.2  4753.7 2085.62
  4814.5  2084.2  4852.7 2084.83  4884.6 2084.52  4904.7 2081.83  4909.7  2082.1
  4951.7 2081.49  4974.8 2080.99    4981 2080.13    4982 2079.63  5023.8 2080.13
  5040.3 2086.47  5049.1 2086.75  5093.6 2092.37  5128.1 2096.28  5222.5 2101.08
  5323.3 2104.85  5405.2 2111.43  5432.4 2112.77  5447.7  2114.7  5476.6 2115.59
#Mann= 8 ,-1 , 0
  4253.2    .035       0  4753.7      .1       0  4852.7     .07       0
  4909.7      .1       0  4951.7     .07       0    4981     .05       0
  5023.8     .07       0  5093.6      .1       0
Bank Sta=4981,5023.8
XS Rating Curve= 0 ,0
Exp/Cntr=0.3,0.1

Type RM Length L Ch R = 1 ,109548  ,539,539,539
BEGIN DESCRIPTION:
South Fork Guadalupe River 168.0
END DESCRIPTION:
XS GIS Cut Line= 3
      1814425.02       13896475.        1814025.       13896375.
      1813825.02     13896025.04
#Sta/Elev= 30
  4587.4 2128.44    4639 2120.74  4646.7 2118.21  4687.9 2109.86  4693.1 2109.71
  4711.1 2104.93  4729.6 2101.59  4752.3 2095.74  4770.4 2089.76  4783.3 2087.41
  4811.6 2085.22  4824.5 2083.19  4852.8 2081.74  4865.7 2079.58  4906.5 2081.99
  4927.6 2082.29  4935.3 2079.54  4940.5 2075.52  4955.1 2073.87  4956.1 2073.37
    4998 2073.87  4999.7 2076.66  5007.6 2077.94  5013.4 2081.01  5022.8 2082.13
    5035 2085.43  5071.9 2090.23  5196.2 2098.56  5332.6 2104.67  5402.8 2107.17
#Mann= 7 ,-1 , 0
  4587.4    .035       0  4729.6      .1       0  4906.5     .07       0
  4955.1     .05       0    4998     .07       0  5071.9      .1       0
  5332.6     .07       0
Bank Sta=4955.1,4998
XS Rating Curve= 0 ,0
Exp/Cntr=0.3,0.1

Type RM Length L Ch R = 1 ,109009  ,549,549,549
BEGIN DESCRIPTION:
South Fork Guadalupe River 167.0
END DESCRIPTION:
XS GIS Cut Line= 3
      1814624.98     13896374.96        1814425.       13896025.
      1813834.81      13895827.9
#Sta/Elev= 30
    4593 2142.59  4780.4 2128.98  4821.1 2123.64  4826.9 2120.85  4842.7 2121.09
  4848.5 2118.21  4864.3 2119.46  4870.1 2116.86  4880.2 2117.11  4885.9 2114.16
  4901.8 2113.54  4907.5  2110.7  4925.8 2109.26  4960.8 2100.52  4966.6 2095.18
  4982.4 2088.54  4988.1  2084.2  4998.7 2082.99  5006.2 2075.97  5007.2 2075.47
  5049.1 2075.97  5059.3 2077.96  5106.6  2077.7  5154.3  2079.5  5322.6 2093.88
  5327.9    2093  5354.2 2096.79  5422.7 2098.61  5588.3 2107.95  5618.3 2109.36
#Mann= 8 ,-1 , 0
    4593    .035       0  4780.4      .1       0  4925.8     .07       0
  5006.2     .05       0  5049.1     .07       0  5106.6    .035       0
  5154.3     .07       0  5588.3      .1       0
Bank Sta=5006.2,5049.1
XS Rating Curve= 0 ,0
Exp/Cntr=0.3,0.1

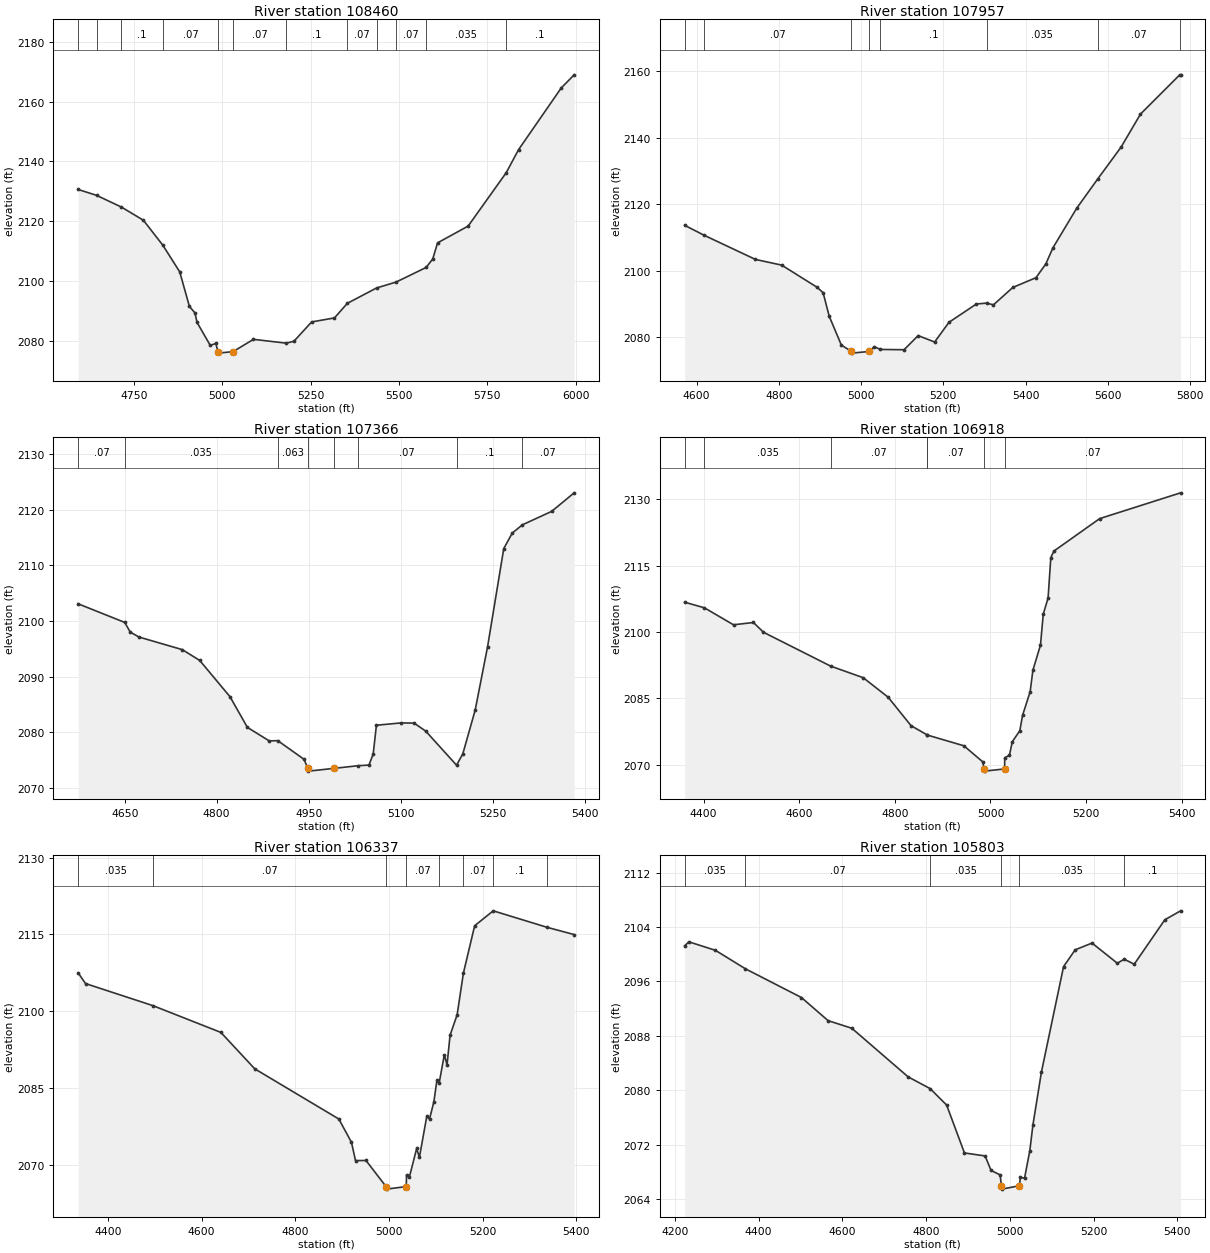
Type RM Length L Ch R = 1 ,108460  ,503,503,503
BEGIN DESCRIPTION:
South Fork Guadalupe River 166.0
END DESCRIPTION:
XS GIS Cut Line= 3
        1814775.     13895875.01        1814575.       13895525.
      1813775.02     13894925.01
#Sta/Elev= 30
  4592.5 2130.59  4644.3 2128.64  4714.8 2124.71  4776.8 2120.32  4831.8 2111.98
  4879.7 2103.05  4907.1  2091.5  4922.9 2089.31  4928.7 2086.15  4966.1 2078.47
  4981.9 2079.12  4987.7 2076.38  4988.7 2075.88  5030.6 2076.38  5088.3 2080.49
  5181.5 2079.21  5202.9 2079.86  5252.9 2086.31  5317.5 2087.65  5353.9 2092.53
  5436.7 2097.67  5491.7 2099.63  5576.9 2104.53  5595.6 2107.39  5609.2 2112.75
  5695.6 2118.35  5803.5 2136.22  5838.3 2143.91  5959.2 2164.56  5995.6 2168.93
#Mann= 12 ,-1 , 0
  4592.5      .1       0  4644.3    .035       0  4714.8      .1       0
  4831.8     .07       0  4987.7     .05       0  5030.6     .07       0
  5181.5      .1       0  5353.9     .07       0  5436.7      .1       0
  5491.7     .07       0  5576.9    .035       0  5803.5      .1       0
Bank Sta=4987.7,5030.6
XS Rating Curve= 0 ,0
Exp/Cntr=0.3,0.1

Type RM Length L Ch R = 1 ,107957  ,591,591,591
BEGIN DESCRIPTION:
South Fork Guadalupe River 165.0
END DESCRIPTION:
XS GIS Cut Line= 3
      1815025.01       13895325.        1814675.       13895075.
      1813925.03     13894875.01
#Sta/Elev= 30
  4570.8  2113.6  4618.3  2110.6  4742.9 2103.34  4806.8 2101.62  4892.8 2094.96
  4907.5 2093.33  4922.3 2086.26  4951.8 2077.58  4976.4 2075.64  4977.4 2075.14
  5019.4 2075.64    5032 2077.08  5046.8 2076.25  5104.4 2076.16  5138.7 2080.41
  5178.8 2078.48  5213.7 2084.42  5280.4 2089.93  5305.6 2090.19  5321.8 2089.67
    5369 2094.91  5425.3 2097.84  5449.2 2101.98  5466.6 2106.85  5524.2 2118.72
  5575.4 2127.54  5632.2 2137.12  5679.5 2147.08    5775 2158.89  5777.1 2158.89
#Mann= 8 ,-1 , 0
  4570.8      .1       0  4618.3     .07       0  4976.4     .05       0
  5019.4     .07       0  5046.8      .1       0  5305.6    .035       0
  5575.4     .07       0    5775      .1       0
Bank Sta=4976.4,5019.4
XS Rating Curve= 0 ,0
Exp/Cntr=0.3,0.1

Type RM Length L Ch R = 1 ,107366  ,448,448,448
BEGIN DESCRIPTION:
South Fork Guadalupe River 164.0
END DESCRIPTION:
XS GIS Cut Line= 3
      1815125.03     13894875.02      1814767.35     13894542.89
        1814725.       13894225.
#Sta/Elev= 30
  4574.2 2103.06  4650.1 2099.72    4659 2097.99  4673.2  2097.1    4744 2094.83
  4772.4 2092.89  4821.7 2086.38  4850.1 2080.87  4885.7 2078.44  4899.7 2078.48
  4942.4 2075.14  4948.7 2073.51  4949.7 2073.01  4991.7 2073.51  5030.3 2073.98
  5048.4  2074.1  5055.3  2076.1  5060.5 2081.25  5100.5 2081.67  5121.9 2081.64
  5140.9  2080.2  5191.2 2074.08  5201.4 2076.11  5221.6 2083.97  5241.8 2095.35
  5268.2 2112.98  5282.1 2115.78  5298.7 2117.26  5346.4 2119.67    5383    2123
#Mann= 8 ,-1 , 0
  4574.2     .07       0  4650.1    .035       0  4899.7    .063       0
  4948.7     .05       0  4991.7    .063       0  5030.3     .07       0
  5191.2      .1       0  5298.7     .07       0
Bank Sta=4948.7,4991.7
XS Rating Curve= 0 ,0
Exp/Cntr=0.3,0.1

Type RM Length L Ch R = 1 ,106918  ,581,581,581
BEGIN DESCRIPTION:
South Fork Guadalupe River 163.0
END DESCRIPTION:
XS GIS Cut Line= 3
      1815304.04     13894932.97        1815125.       13894325.
      1814774.99       13894125.
#Sta/Elev= 30
  4360.6 2106.76  4401.9 2105.49  4462.7 2101.65  4504.4 2102.17  4525.3 2099.96
  4665.7 2092.31  4733.9 2089.68  4785.9 2085.28  4833.9 2078.83  4866.3 2076.82
  4867.9 2076.71  4944.4 2074.28    4984 2070.63  4986.5 2069.05  4987.5 2068.55
  5029.6 2069.05  5029.7 2071.53  5039.7 2072.19  5045.5 2075.19  5061.3 2077.69
  5067.1 2081.19  5082.9 2086.51  5088.7 2091.39  5104.5 2097.06  5110.3 2104.05
  5120.4 2107.71  5126.1 2116.84  5132.6 2118.33  5228.3 2125.67  5397.5  2131.5
#Mann= 7 ,-1 , 0
  4360.6     .07       0  4401.9    .035       0  4665.7     .07       0
  4866.3    .035       0  4867.9     .07       0  4986.5     .05       0
  5029.6     .07       0
Bank Sta=4986.5,5029.6
XS Rating Curve= 0 ,0
Exp/Cntr=0.3,0.1

Type RM Length L Ch R = 1 ,106337  ,534,534,534
BEGIN DESCRIPTION:
South Fork Guadalupe River 162.0
END DESCRIPTION:
XS GIS Cut Line= 3
      1815511.93     13894960.07        1815675.       13894325.
      1815474.99     13893974.98
#Sta/Elev= 30
  4336.6 2107.49  4352.2 2105.42    4496 2101.11  4641.2 2095.88  4713.5 2088.77
    4893 2078.97    4920 2074.42  4928.6 2070.85    4951 2070.87  4993.8 2065.78
  4994.8 2065.28  5036.9 2065.78  5037.6 2068.06  5043.4 2067.56  5059.2 2073.22
    5065 2071.47  5080.8 2079.51  5086.6 2078.96  5095.9 2082.32  5102.4 2086.53
  5107.1 2085.94  5118.2 2091.51    5124 2089.55  5130.5 2095.33  5145.6 2099.33
  5158.9 2107.43    5183 2116.71  5222.6 2119.62    5338 2116.39  5395.4 2114.98
#Mann= 8 ,-1 , 0
  4336.6    .035       0    4496     .07       0  4993.8     .05       0
  5036.9     .07       0  5107.1    .035       0  5158.9     .07       0
  5222.6      .1       0    5338     .07       0
Bank Sta=4993.8,5036.9
XS Rating Curve= 0 ,0
Exp/Cntr=0.3,0.1

Type RM Length L Ch R = 1 ,105803  ,540,540,540
BEGIN DESCRIPTION:
South Fork Guadalupe River 161.0
END DESCRIPTION:
XS GIS Cut Line= 3
      1815650.38     13895004.14        1816175.       13894425.
      1816224.99     13894025.04
#Sta/Elev= 30
  4223.5 2101.23  4233.5 2101.82    4297 2100.57  4368.7 2097.85  4502.4 2093.63
    4566 2090.23  4622.7 2089.11  4757.2 2081.96  4809.6 2080.24  4849.1 2077.82
  4891.7 2070.77  4941.1 2070.33  4955.2  2068.2  4976.9 2067.54    4980 2065.95
    4981 2065.45  5023.1 2065.95  5025.1 2067.19  5035.2 2067.05  5047.8 2071.09
  5055.3 2074.91  5075.5 2082.65  5128.4 2098.17  5156.1 2100.64  5196.4 2101.64
  5256.9 2098.67  5273.2 2099.27  5297.2 2098.53  5370.2 2105.06    5408 2106.38
#Mann= 6 ,-1 , 0
  4223.5    .035       0  4368.7     .07       0  4809.6    .035       0
    4980     .05       0  5023.1    .035       0  5273.2      .1       0
Bank Sta=4980,5023.1
XS Rating Curve= 0 ,0
Exp/Cntr=0.3,0.1

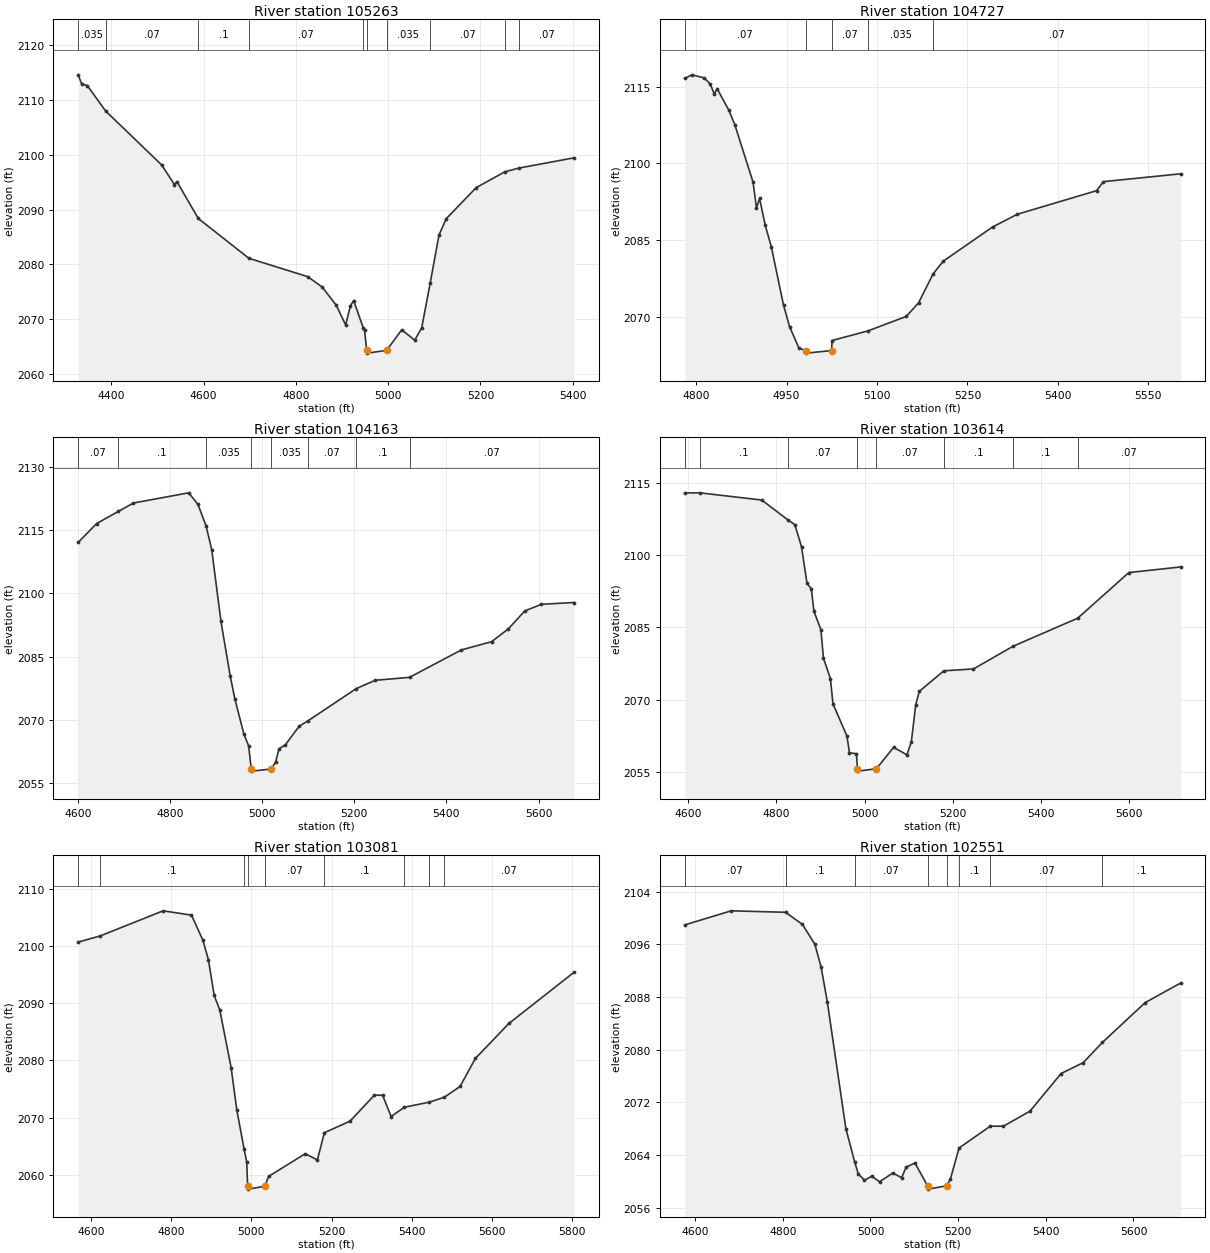
Type RM Length L Ch R = 1 ,105263  ,536,536,536
BEGIN DESCRIPTION:
South Fork Guadalupe River 160.0
END DESCRIPTION:
XS GIS Cut Line= 3
      1816486.54     13895332.09        1816625.       13894675.
      1816824.99     13894325.03
#Sta/Elev= 30
  4328.5 2114.58  4335.7 2112.96  4348.2 2112.61    4388 2107.97  4509.5 2098.12
  4537.1 2094.54  4542.3  2095.1  4588.7 2088.36  4698.3  2081.1  4825.7 2077.75
  4856.9 2075.87  4887.6 2072.53    4908 2068.93  4918.3 2072.43  4925.3 2073.38
  4945.9 2068.45  4948.9 2067.98  4953.5 2064.29  4954.5 2063.79  4996.7 2064.29
  5029.5 2068.04  5057.6 2066.16  5072.7 2068.38  5091.1 2076.54  5110.2 2085.33
    5126 2088.33  5190.8 2093.99  5252.4 2096.86  5282.6 2097.55  5403.1 2099.44
#Mann= 10 ,-1 , 0
  4328.5    .035       0    4388     .07       0  4588.7      .1       0
  4698.3     .07       0  4945.9    .035       0  4953.5    .035       0
  4996.7    .035       0  5091.1     .07       0  5252.4      .1       0
  5282.6     .07       0
Bank Sta=4953.5,4996.7
XS Rating Curve= 0 ,0
Exp/Cntr=0.3,0.1

Type RM Length L Ch R = 1 ,104727  ,564,564,564
BEGIN DESCRIPTION:
South Fork Guadalupe River 159.0
END DESCRIPTION:
XS GIS Cut Line= 3
      1817042.82      13895047.2        1817075.       13894825.
      1816952.15     13894239.77
#Sta/Elev= 30
    4781 2116.61  4793.3 2117.31  4813.5  2116.7  4823.6 2115.48  4829.9 2113.57
  4834.9 2114.57    4854 2110.44  4864.1 2107.57  4894.4 2096.31  4900.1 2091.25
  4905.2 2093.13  4914.6 2087.87  4924.7 2083.65  4944.9 2072.25    4955 2068.01
  4970.4 2063.87  4981.4 2063.35  4982.4 2062.85  5024.6 2063.35  5025.4 2065.32
  5085.5 2067.22  5148.6 2070.04    5169 2072.71    5193 2078.36  5209.9 2080.85
  5291.6 2087.53  5332.5 2090.02  5464.1 2094.64  5475.5 2096.41  5603.5 2097.94
#Mann= 5 ,-1 , 0
    4781     .07       0  4981.4     .05       0  5024.6     .07       0
  5085.5    .035       0    5193     .07       0
Bank Sta=4981.4,5024.6
XS Rating Curve= 0 ,0
Exp/Cntr=0.3,0.1

Type RM Length L Ch R = 1 ,104163  ,549,549,549
BEGIN DESCRIPTION:
South Fork Guadalupe River 158.0
END DESCRIPTION:
XS GIS Cut Line= 3
      1817924.96       13894575.        1817525.       13894575.
      1816960.95     13894200.53
#Sta/Elev= 30
  4600.4 2112.06  4640.4 2116.51  4687.3 2119.38  4720.4 2121.38  4840.4 2123.79
  4860.4 2121.05  4878.2 2115.93  4890.4 2110.29  4910.4 2093.35  4930.4 2080.48
  4940.4 2075.09  4960.4  2066.6  4970.4 2063.94  4976.3 2058.42  4977.3 2057.92
  5019.5 2058.42  5028.9 2060.02  5036.4 2063.19    5050 2064.13  5080.1 2068.52
  5100.1 2069.88  5204.2 2077.45  5245.4 2079.42    5320 2080.12  5432.5 2086.61
    5498 2088.55  5534.1 2091.55  5570.2 2095.83  5606.3 2097.41  5677.4 2097.83
#Mann= 8 ,-1 , 0
  4600.4     .07       0  4687.3      .1       0  4878.2    .035       0
  4976.3    .035       0  5019.5    .035       0  5100.1     .07       0
  5204.2      .1       0    5320     .07       0
Bank Sta=4976.3,5019.5
XS Rating Curve= 0 ,0
Exp/Cntr=0.3,0.1

Type RM Length L Ch R = 1 ,103614  ,533,533,533
BEGIN DESCRIPTION:
South Fork Guadalupe River 157.0
END DESCRIPTION:
XS GIS Cut Line= 3
      1817875.01     13894425.01        1817675.       13894075.
      1816958.41       13894157.
#Sta/Elev= 30
  4591.9 2112.94    4626 2112.96  4766.8 2111.46  4826.1 2107.33  4841.7 2106.35
  4856.8 2101.76  4869.1 2094.23  4879.1 2093.01  4884.9 2088.39  4900.7 2084.56
  4906.5 2078.65  4922.3 2074.39  4928.1 2069.14  4959.8 2062.45  4965.5 2058.98
  4981.4 2058.78  4983.5 2055.67  4984.5 2055.17  5026.7 2055.67  5065.5  2060.1
  5095.7 2058.56  5105.7 2061.19  5115.8    2069  5123.9 2071.74  5179.5    2076
  5246.7 2076.39  5336.4  2081.1    5483 2086.93  5598.9  2096.4  5716.3 2097.57
#Mann= 8 ,-1 , 0
  4591.9     .07       0    4626      .1       0  4826.1     .07       0
  4983.5     .05       0  5026.7     .07       0  5179.5      .1       0
  5336.4      .1       0    5483     .07       0
Bank Sta=4983.5,5026.7
XS Rating Curve= 0 ,0
Exp/Cntr=0.3,0.1

Type RM Length L Ch R = 1 ,103081  ,530,530,530
BEGIN DESCRIPTION:
South Fork Guadalupe River 156.0
END DESCRIPTION:
XS GIS Cut Line= 3
      1818074.98     13893874.98        1817775.       13893575.
      1816974.98       13893425.
#Sta/Elev= 30
  4567.6  2100.7  4622.5 2101.78  4779.7 2106.17  4850.4 2105.42  4878.7 2101.06
  4892.8 2097.59    4907 2091.38  4921.1 2088.82  4949.4 2078.75  4963.6 2071.32
  4981.8  2064.5  4988.3 2062.24  4990.6    2058  4991.6  2057.5  5033.8    2058
  5042.7 2059.71  5134.3 2063.69  5164.8 2062.61  5182.2 2067.37  5246.2 2069.38
  5307.2 2073.95  5327.6 2073.91  5348.8  2070.2  5381.9 2071.82  5443.6  2072.7
  5481.5 2073.56  5520.9 2075.45  5559.1 2080.35    5643 2086.48  5805.8 2095.44
#Mann= 9 ,-1 , 0
  4567.6     .07       0  4622.5      .1       0  4981.8     .07       0
  4990.6     .05       0  5033.8     .07       0  5182.2      .1       0
  5381.9     .07       0  5443.6      .1       0  5481.5     .07       0
Bank Sta=4990.6,5033.8
XS Rating Curve= 0 ,0
Exp/Cntr=0.3,0.1

Type RM Length L Ch R = 1 ,102551  ,298,298,298
BEGIN DESCRIPTION:
South Fork Guadalupe River 155.0
END DESCRIPTION:
XS GIS Cut Line= 3
      1818075.02     13893425.02        1817775.       13893125.
        1817075.       13893225.
#Sta/Elev= 30
  4576.2 2098.95  4682.3 2101.09  4806.3 2100.87  4844.9 2099.02  4873.2 2096.02
  4887.4 2092.56  4901.5 2087.32  4943.9 2068.04    4964 2062.97  4972.2 2061.17
  4986.3 2060.19    5003  2060.8  5020.7 2059.96    5051 2061.28  5071.2 2060.58
  5081.3 2062.17  5101.5  2062.8  5130.4 2059.34  5131.4 2058.84  5173.6 2059.34
  5182.3 2060.35  5202.2 2065.09  5273.5  2068.4  5303.5 2068.39  5364.1 2070.69
  5434.9 2076.39  5485.4 2078.04  5529.1 2081.11  5626.8 2087.16  5707.6 2090.13
#Mann= 8 ,-1 , 0
  4576.2     .07       0  4806.3      .1       0    4964     .07       0
  5130.4     .05       0  5173.6     .07       0  5202.2      .1       0
  5273.5     .07       0  5529.1      .1       0
Bank Sta=5130.4,5173.6
XS Rating Curve= 0 ,0
Exp/Cntr=0.3,0.1

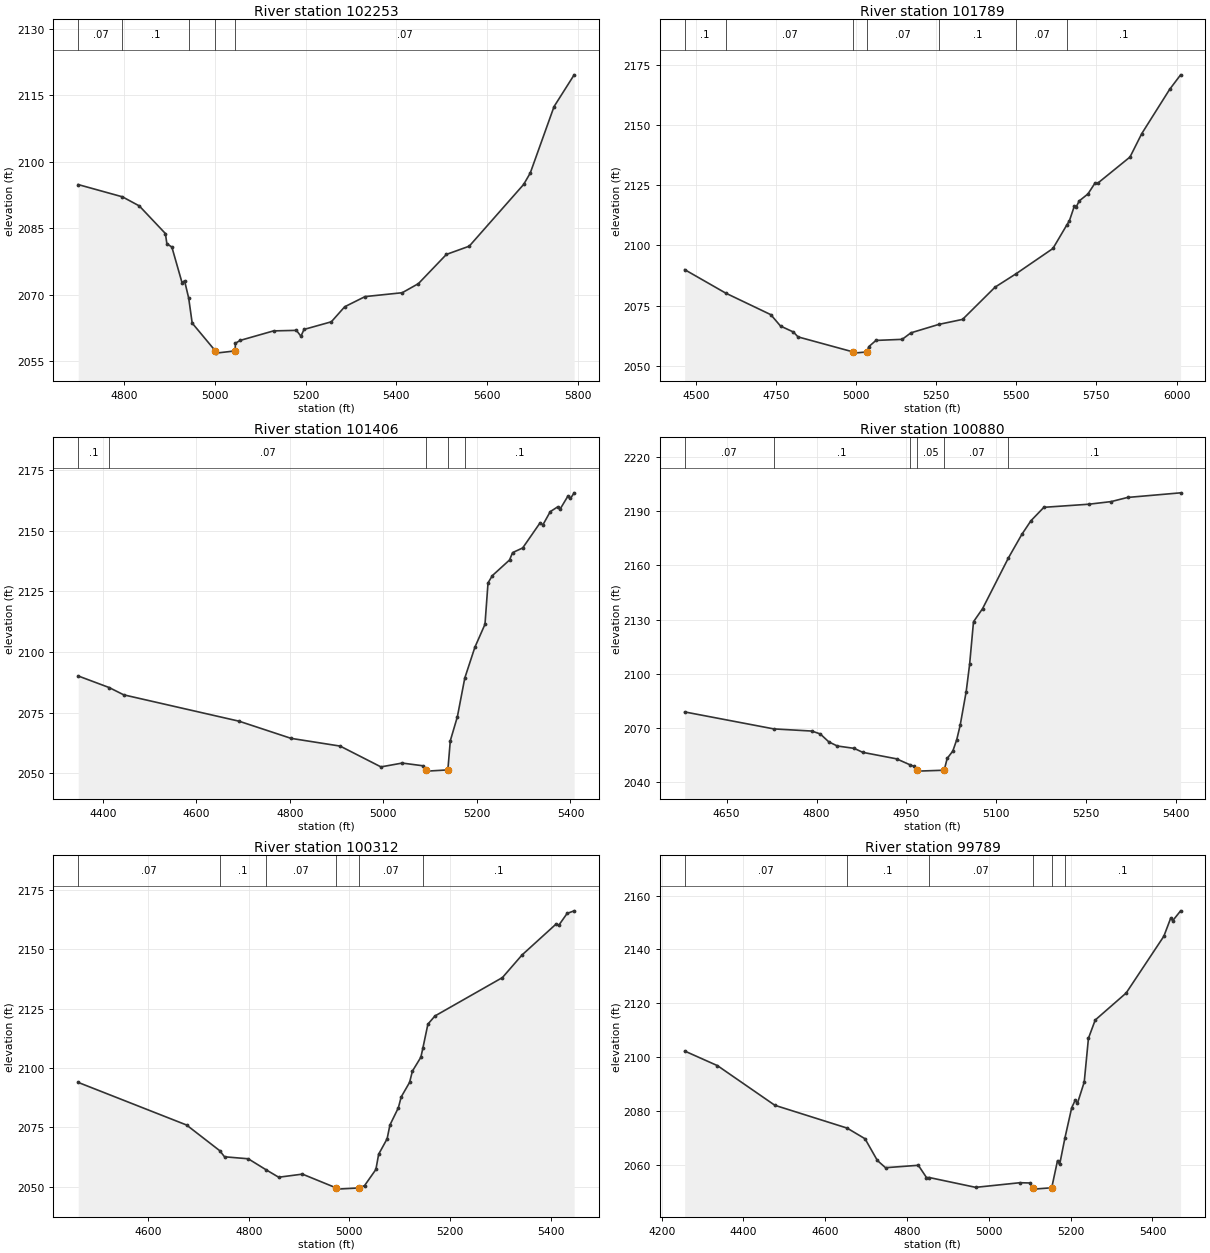
Type RM Length L Ch R = 1 ,102253  ,464,464,464
BEGIN DESCRIPTION:
Mapping XS b987eaf5
END DESCRIPTION:
XS GIS Cut Line= 3
      1817981.28     13893035.61      1817869.42     13892874.65
      1817065.32     13892476.03
#Sta/Elev= 30
  4698.6 2094.85  4796.1 2092.09  4833.3 2090.04  4890.8 2083.82  4894.1 2081.52
  4905.1 2080.77  4927.5 2072.75  4933.1 2073.17  4942.2 2069.26  4949.9 2063.64
    5001 2057.37    5002 2056.87  5044.6 2057.37  5045.2 2059.09  5055.8 2059.74
  5129.3 2061.88  5179.7    2062  5189.7 2060.68  5196.5 2062.21  5256.7 2063.93
  5286.2 2067.32  5331.1 2069.61    5413 2070.48  5448.7 2072.53  5510.4 2079.11
  5560.8 2080.97  5680.8 2094.89  5695.3 2097.45  5747.8 2112.43  5792.1 2119.58
#Mann= 5 ,-1 , 0
  4698.6     .07       0  4796.1      .1       0  4942.2     .07       0
    5001     .05       0  5044.6     .07       0
Bank Sta=5001,5044.6
XS Rating Curve= 0 ,0
Exp/Cntr=0.3,0.1

Type RM Length L Ch R = 1 ,101789  ,383,383,383
BEGIN DESCRIPTION:
Mapping XS 5b568759
END DESCRIPTION:
XS GIS Cut Line= 3
       1817951.8     13892870.75       1817884.8     13892419.63
       1816955.9     13891846.98
#Sta/Elev= 30
  4465.5 2089.95  4593.8 2080.17  4734.2 2071.23  4764.5 2066.51  4804.9 2064.01
  4819.1    2062    4991 2055.75    4992 2055.25  5034.6 2055.75  5039.9 2057.94
  5062.3 2060.53  5144.1 2060.98  5171.3 2063.68  5258.7  2067.2  5332.5 2069.27
  5433.9 2082.67  5498.8 2088.18  5614.4 2098.73  5657.7  2108.5  5665.7 2110.21
  5681.1 2116.29    5687    2116  5696.5 2118.51  5723.6 2121.39  5744.9 2125.75
  5754.4 2125.89  5854.9 2136.75  5891.6 2146.48  5978.6 2164.87  6012.8  2170.9
#Mann= 7 ,-1 , 0
  4465.5      .1       0  4593.8     .07       0    4991     .05       0
  5034.6     .07       0  5258.7      .1       0  5498.8     .07       0
  5657.7      .1       0
Bank Sta=4991,5034.6
XS Rating Curve= 0 ,0
Exp/Cntr=0.3,0.1

Type RM Length L Ch R = 1 ,101406  ,526,526,526
BEGIN DESCRIPTION:
South Fork Guadalupe River 154.0
END DESCRIPTION:
XS GIS Cut Line= 3
        1817975.     13892874.97        1818075.       13892225.
      1818424.97     13892025.02
#Sta/Elev= 30
  4347.2 2090.12  4413.3 2085.36  4444.6 2082.35  4691.2  2071.5  4802.5 2064.43
  4907.4 2061.25  4994.7 2052.68  5040.1 2054.26  5085.4 2053.12  5092.1 2051.44
  5093.1 2050.94  5137.8 2051.44    5143 2063.44  5158.1  2073.3    5174 2089.27
  5195.6 2101.96  5217.2 2111.41  5223.7 2128.46    5233 2131.45  5269.7 2137.88
  5276.2 2140.91  5297.8 2142.83  5335.2 2153.22    5341 2152.33  5356.8 2157.79
  5372.7 2159.75  5378.4    2159  5394.3  2164.1    5400 2163.21  5407.9 2165.53
#Mann= 5 ,-1 , 0
  4347.2      .1       0  4413.3     .07       0  5092.1     .05       0
  5137.8     .07       0    5174      .1       0
Bank Sta=5092.1,5137.8
XS Rating Curve= 0 ,0
Exp/Cntr=0.3,0.1

Type RM Length L Ch R = 1 ,100880  ,568,568,568
BEGIN DESCRIPTION:
South Fork Guadalupe River 153.0
END DESCRIPTION:
XS GIS Cut Line= 3
      1818125.02     13892774.98        1818425.       13892475.
      1818774.96     13892275.02
#Sta/Elev= 30
    4580 2078.86  4728.7 2069.46  4792.1 2068.27  4806.2 2066.67  4820.4 2062.29
  4834.5 2060.01  4862.8 2058.69    4877 2056.49  4933.5 2052.89  4955.2 2049.69
  4961.8 2048.83  4967.2 2046.59  4968.2 2046.09  5012.9 2046.59  5017.9 2053.14
  5027.3 2057.19  5033.8 2063.46  5039.5 2071.36  5049.6 2090.11  5055.3 2105.12
  5061.8 2128.78  5076.9 2136.01  5120.1 2164.15  5142.4 2177.12  5157.6 2184.68
  5179.2 2192.12    5254 2193.83  5291.5 2195.29  5318.8 2197.58  5407.3 2200.14
#Mann= 6 ,-1 , 0
    4580     .07       0  4728.7      .1       0  4955.2     .07       0
  4967.2     .05       0  5012.9     .07       0  5120.1      .1       0
Bank Sta=4967.2,5012.9
XS Rating Curve= 0 ,0
Exp/Cntr=0.3,0.1

Type RM Length L Ch R = 1 ,100312  ,523,523,523
BEGIN DESCRIPTION:
South Fork Guadalupe River 152.0
END DESCRIPTION:
XS GIS Cut Line= 3
      1818124.97     13893175.01        1818625.       13892975.
      1818825.02     13892574.97
#Sta/Elev= 30
  4461.1 2093.95  4676.5 2076.01  4742.4  2065.2  4751.9 2062.63  4799.1 2061.79
  4834.6 2057.15  4859.6 2054.02  4906.8 2055.33  4974.1 2049.51  4975.1 2049.01
  5019.8 2049.51  5030.4 2050.53  5052.8 2057.29  5058.3 2063.71  5075.1  2070.2
  5080.7    2076  5097.5 2083.29  5103.1 2087.83  5119.8 2093.98  5125.4 2098.71
  5142.2 2104.56  5146.2  2108.4  5156.2 2118.49  5170.2 2121.93  5304.3  2138.1
  5343.4 2147.64  5410.5 2160.55  5416.1 2160.06  5432.9 2165.11  5446.9 2166.21
#Mann= 6 ,-1 , 0
  4461.1     .07       0  4742.4      .1       0  4834.6     .07       0
  4974.1     .05       0  5019.8     .07       0  5146.2      .1       0
Bank Sta=4974.1,5019.8
XS Rating Curve= 0 ,0
Exp/Cntr=0.3,0.1

Type RM Length L Ch R = 1 ,99789   ,506,506,506
BEGIN DESCRIPTION:
South Fork Guadalupe River 151.0
END DESCRIPTION:
XS GIS Cut Line= 3
      1818024.98       13893475.        1818775.       13893425.
      1819225.04     13893525.01
#Sta/Elev= 30
  4256.2 2102.24  4336.4 2096.81  4476.7 2082.08  4653.3 2073.61  4697.2 2069.64
  4727.3 2061.58  4747.3 2058.88  4827.5 2059.78  4847.5 2055.23  4854.6 2055.22
  4967.8 2051.58  5075.7  2053.3  5100.1 2053.21    5108 2051.42    5109 2050.92
  5153.7 2051.42  5167.9 2061.53  5173.1 2060.08  5185.9 2069.87  5202.5 2081.12
  5211.5 2084.09  5216.6 2082.79  5233.2 2090.72  5243.5 2106.97  5260.1 2113.77
  5335.7  2123.8  5427.9 2144.91  5444.5 2151.57  5449.7 2150.71  5468.9 2154.35
#Mann= 6 ,-1 , 0
  4256.2     .07       0  4653.3      .1       0  4854.6     .07       0
    5108     .05       0  5153.7     .07       0  5185.9      .1       0
Bank Sta=5108,5153.7
XS Rating Curve= 0 ,0
Exp/Cntr=0.3,0.1

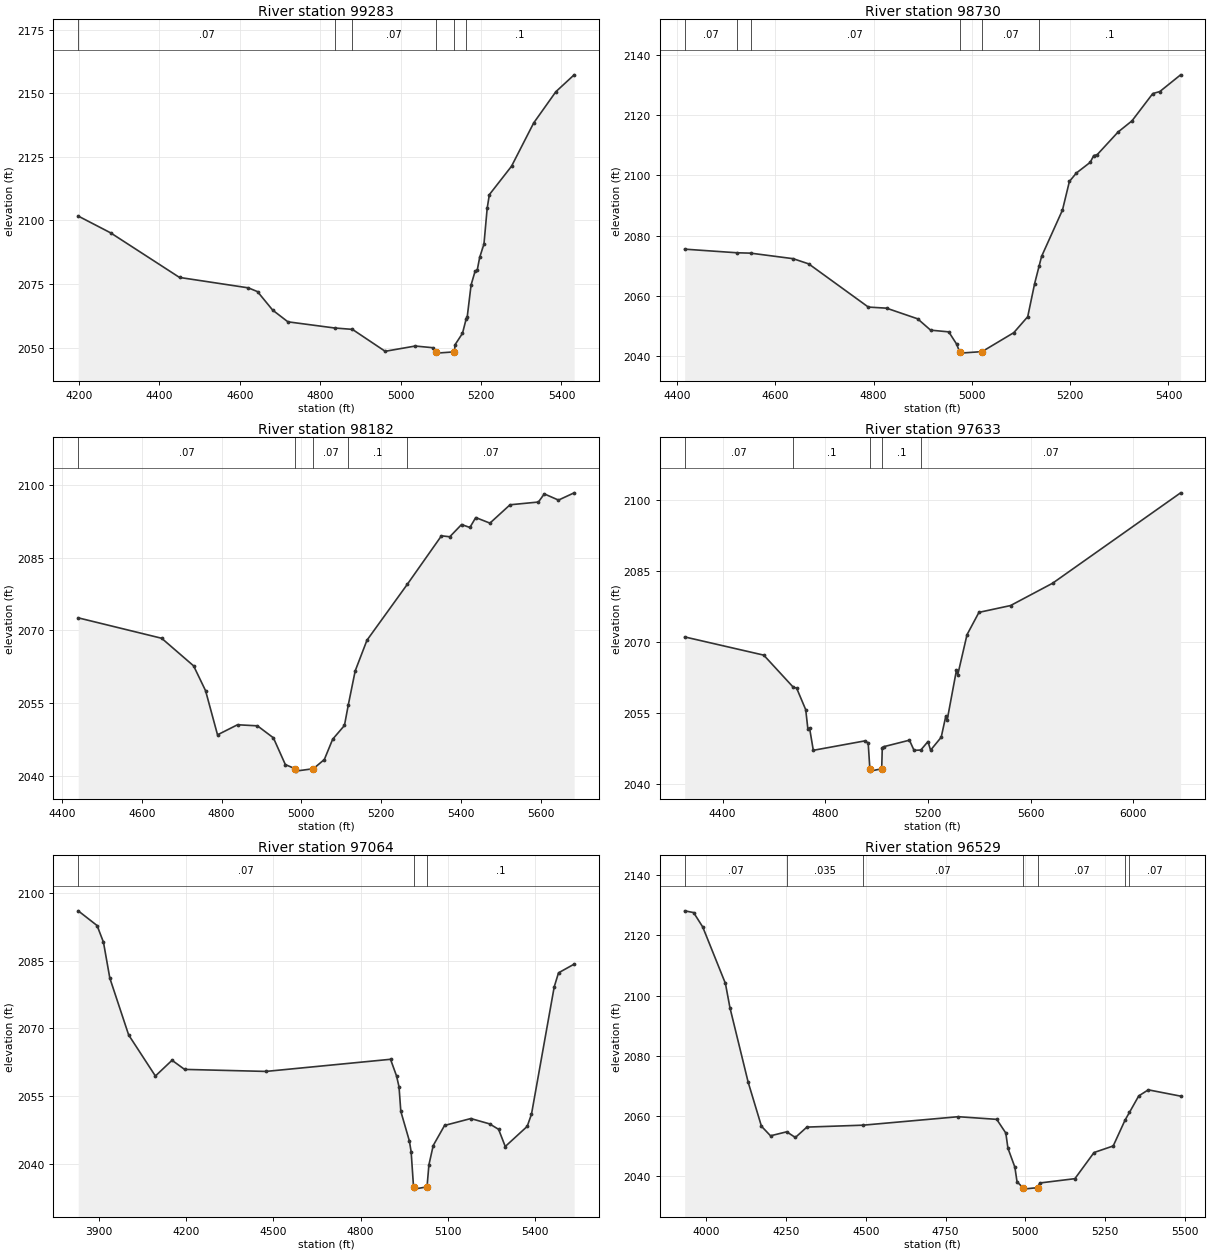
Type RM Length L Ch R = 1 ,99283   ,553,553,553
BEGIN DESCRIPTION:
South Fork Guadalupe River 150.0
END DESCRIPTION:
XS GIS Cut Line= 3
      1818075.04     13893974.99        1818875.       13893875.
      1819275.02     13893724.99
#Sta/Elev= 30
  4198.2 2101.74  4278.8 2095.14  4450.1 2077.61  4621.4 2073.51  4644.1 2072.03
  4681.9 2064.75  4719.7 2060.16    4836 2057.73  4880.1 2057.19  4961.6 2048.57
  5036.4 2050.64    5080 2049.98  5088.3 2048.35  5089.3 2047.85    5134 2048.35
  5135.2  2051.1  5153.9 2055.64    5163 2061.27  5165.5 2061.87  5175.3 2074.67
  5185.1 2079.97  5190.4 2080.35  5196.6 2085.46  5207.3 2090.75  5215.3 2104.79
  5220.7 2110.16  5275.8 2121.32    5331 2138.36  5386.2 2150.65  5431.6 2157.27
#Mann= 6 ,-1 , 0
  4198.2     .07       0    4836      .1       0  4880.1     .07       0
  5088.3     .05       0    5134     .07       0    5163      .1       0
Bank Sta=5088.3,5134
XS Rating Curve= 0 ,0
Exp/Cntr=0.3,0.1

Type RM Length L Ch R = 1 ,98730   ,548,548,548
BEGIN DESCRIPTION:
South Fork Guadalupe River 149.0
END DESCRIPTION:
XS GIS Cut Line= 3
      1818470.01      13894559.4        1819025.       13894375.
      1819325.01     13894074.99
#Sta/Elev= 30
  4415.6  2075.5  4521.7  2074.3  4549.9 2074.17  4636.3 2072.33    4668  2070.6
  4789.3 2056.24  4826.3 2055.88  4889.6 2052.34    4916 2048.57  4952.9    2048
  4968.8 2043.96  4974.9 2041.43  4975.9 2040.93  5020.7 2041.43  5085.3 2047.74
  5113.6 2053.04  5127.7 2064.08  5136.9 2069.96  5141.8 2073.09  5184.3  2088.5
  5198.4 2098.01  5212.6 2100.82  5240.8 2104.37  5247.9 2106.63    5255 2106.92
  5297.4 2114.44  5325.7 2118.15  5368.1 2127.24  5382.3 2127.89  5424.7 2133.46
#Mann= 6 ,-1 , 0
  4415.6     .07       0  4521.7      .1       0  4549.9     .07       0
  4974.9     .05       0  5020.7     .07       0  5136.9      .1       0
Bank Sta=4974.9,5020.7
XS Rating Curve= 0 ,0
Exp/Cntr=0.3,0.1

Type RM Length L Ch R = 1 ,98182   ,549,549,549
BEGIN DESCRIPTION:
South Fork Guadalupe River 148.0
END DESCRIPTION:
XS GIS Cut Line= 4
       1818615.8     13894854.89        1819175.       13894875.
        1819425.       13894525.      1819573.46     13894318.75
#Sta/Elev= 30
  4440.4 2072.59  4649.7 2068.37  4729.8 2062.67  4759.8 2057.54  4789.8 2048.42
  4839.9  2050.5  4889.9 2050.28  4929.9  2047.8  4959.9 2042.27  4984.4 2041.42
  4985.4 2040.92  5030.2 2041.42  5057.7 2043.32  5078.6 2047.52  5108.1 2050.35
  5117.8 2054.62  5135.1 2061.64  5164.6 2067.97  5266.2 2079.57  5351.4 2089.54
  5372.3 2089.34  5401.8 2091.87  5422.7 2091.26  5437.4 2093.31    5473 2092.16
  5523.4 2095.95  5594.6 2096.52  5609.3  2098.2  5644.9 2096.92  5684.2 2098.42
#Mann= 5 ,-1 , 0
  4440.4     .07       0  4984.4     .05       0  5030.2     .07       0
  5117.8      .1       0  5266.2     .07       0
Bank Sta=4984.4,5030.2
XS Rating Curve= 0 ,0
Exp/Cntr=0.3,0.1

Type RM Length L Ch R = 1 ,97633   ,569,569,569
BEGIN DESCRIPTION:
South Fork Guadalupe River 147.0
END DESCRIPTION:
XS GIS Cut Line= 4
      1818614.14     13894937.46        1819225.       13895375.
        1819625.       13895475.      1820368.71     13895286.19
#Sta/Elev= 30
  4252.6 2071.14  4560.5 2067.29    4676 2060.47  4688.3 2060.34  4723.9 2055.75
  4732.5 2051.58  4738.7 2051.93  4753.4 2047.17  4954.8 2049.17  4967.1 2048.72
  4973.6 2043.27  4974.6 2042.77  5019.7 2043.27    5022 2047.74  5027.2 2047.93
  5127.7 2049.31  5145.7 2047.16    5172 2047.23  5199.8 2049.02  5210.1  2047.2
  5251.4 2049.93  5269.4 2054.42  5274.6 2053.56  5310.6 2064.05  5315.8 2063.13
  5351.9 2071.61  5398.3 2076.33  5521.3 2077.77  5685.1 2082.49  6183.6  2101.6
#Mann= 5 ,-1 , 0
  4252.6     .07       0    4676      .1       0  4973.6     .05       0
  5019.7      .1       0    5172     .07       0
Bank Sta=4973.6,5019.7
XS Rating Curve= 0 ,0
Exp/Cntr=0.3,0.1

Type RM Length L Ch R = 1 ,97064   ,535,535,535
BEGIN DESCRIPTION:
South Fork Guadalupe River 146.0
END DESCRIPTION:
XS GIS Cut Line= 3
      1818533.57     13896814.88        1819225.       13895875.
      1819724.97     13895675.01
#Sta/Elev= 30
  3828.9 2096.08  3893.7 2092.82  3915.7 2089.13  3937.6 2081.16  4002.4 2068.55
  4094.3 2059.45  4151.5 2062.94  4194.6 2060.92  4474.3 2060.47  4902.8 2063.16
  4923.6 2059.44    4932 2057.06  4938.2 2051.61  4967.5 2045.08  4973.7 2042.65
  4981.9 2034.87  4982.9 2034.37  5028.3 2034.87  5034.8 2039.76  5049.6 2044.04
  5088.6 2048.49  5178.8 2050.02  5243.4 2048.84  5274.4 2047.63  5297.3 2043.82
  5372.7 2048.28  5387.5 2050.99  5465.6  2079.2  5480.4 2082.33  5534.2 2084.26
#Mann= 3 ,-1 , 0
  3828.9     .07       0  4981.9     .05       0  5028.3      .1       0
Bank Sta=4981.9,5028.3
XS Rating Curve= 0 ,0
Exp/Cntr=0.3,0.1

Type RM Length L Ch R = 1 ,96529   ,546,546,546
BEGIN DESCRIPTION:
South Fork Guadalupe River 145.0
END DESCRIPTION:
XS GIS Cut Line= 3
      1818774.99     13897125.01        1819475.       13896325.
      1819966.26      13896310.7
#Sta/Elev= 30
  3932.3 2128.16  3960.3 2127.58  3988.8 2122.82    4060 2104.06  4074.2 2095.99
  4131.2 2071.31  4172.9 2056.66  4201.4 2053.48  4252.1 2054.81  4279.2 2052.92
  4315.3 2056.37  4491.8 2057.01  4789.8 2059.82  4910.4 2058.94  4938.9 2054.39
  4945.5 2049.37  4967.3 2043.06    4974 2038.25  4992.1 2036.28  4993.1 2035.78
  5038.5 2036.28  5045.4 2037.82  5155.4 2039.25  5215.4 2047.93  5275.5 2050.11
  5312.8 2058.73  5326.3 2061.23  5355.5 2066.72  5385.5 2068.74  5486.8 2066.65
#Mann= 7 ,-1 , 0
  3932.3     .07       0  4252.1    .035       0  4491.8     .07       0
  4992.1     .05       0  5038.5     .07       0  5312.8      .1       0
  5326.3     .07       0
Bank Sta=4992.1,5038.5
XS Rating Curve= 0 ,0
Exp/Cntr=0.3,0.1