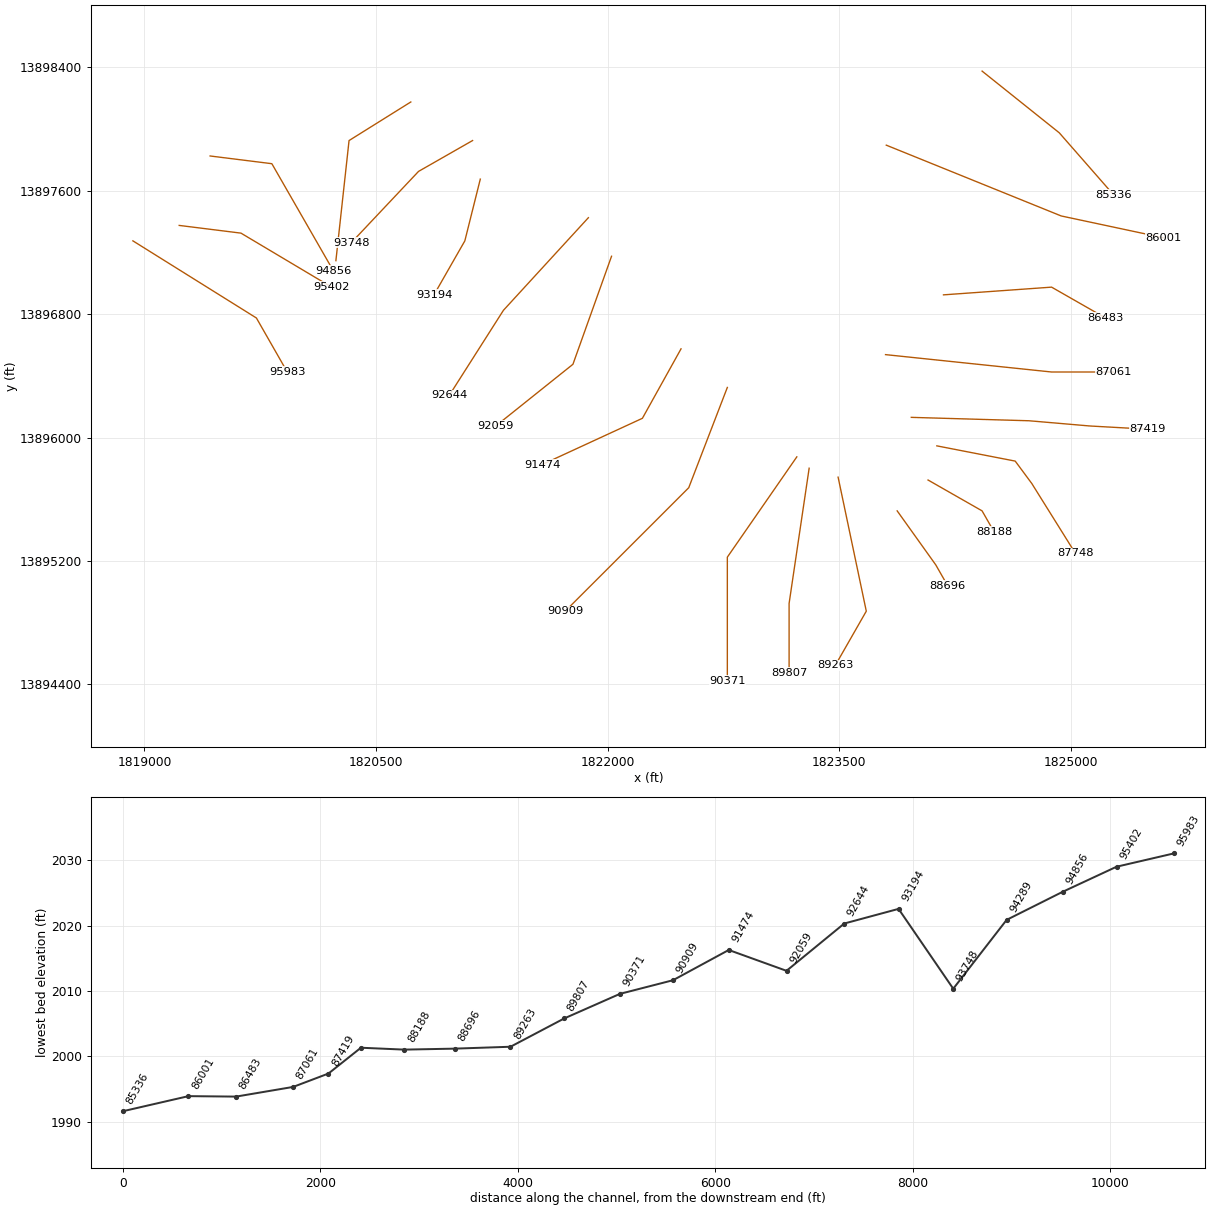
HEC-RAS study South Fork Guadalupe River.prj: South Fork Guadalupe River Base Level Engineering

--- South Fork Guadalupe River.g01 (geometry) --- (continued)

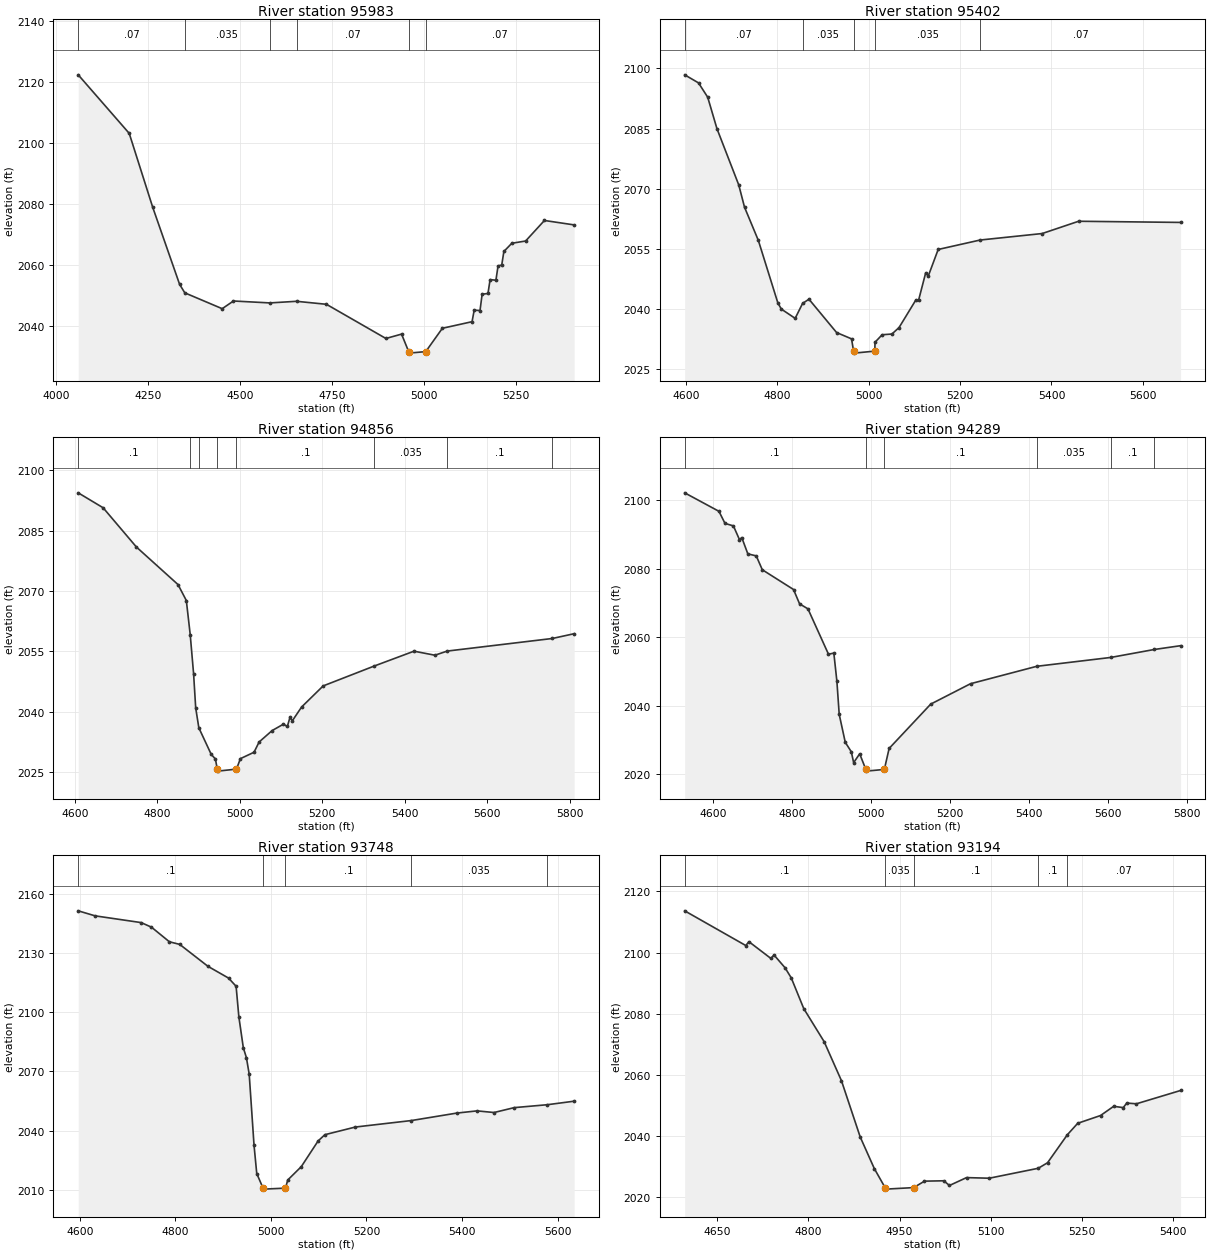
Type RM Length L Ch R = 1 ,95983   ,581,581,581
BEGIN DESCRIPTION:
South Fork Guadalupe River 144.0
END DESCRIPTION:
XS GIS Cut Line= 3
      1818925.04     13897274.97        1819725.       13896775.
      1819925.02     13896424.97
#Sta/Elev= 30
  4060.5 2122.26    4199 2103.08  4262.7 2078.89  4335.8 2053.61  4349.9 2050.83
  4451.4 2045.64    4482 2048.16  4580.9 2047.53  4653.2 2048.06  4734.4 2047.08
  4895.9 2035.88  4938.4 2037.31  4957.7 2031.58  4958.7 2031.08  5004.1 2031.58
  5049.2 2039.22  5129.8 2041.38  5135.6 2045.15  5151.4 2045.04  5157.2 2050.39
    5173 2050.62  5178.8 2055.16  5194.6 2054.97  5200.4 2059.66  5210.4 2059.95
  5216.2 2064.39  5237.8 2067.08  5275.2 2067.81  5326.3 2074.54    5407 2073.09
#Mann= 6 ,-1 , 0
  4060.5     .07       0  4349.9    .035       0  4580.9      .1       0
  4653.2     .07       0  4957.7     .05       0  5004.1     .07       0
Bank Sta=4957.7,5004.1
XS Rating Curve= 0 ,0
Exp/Cntr=0.3,0.1

Type RM Length L Ch R = 1 ,95402   ,546,546,546
BEGIN DESCRIPTION:
South Fork Guadalupe River 143.0
END DESCRIPTION:
XS GIS Cut Line= 3
      1819224.98       13897375.        1819625.       13897325.
       1820211.4     13896975.47
#Sta/Elev= 30
  4596.9 2098.41  4627.2  2096.4  4647.3 2092.83  4667.5 2085.01  4715.3 2070.96
  4727.9 2065.42  4758.2 2057.13    4801 2041.52  4808.6 2040.01  4838.8 2037.71
  4855.1 2041.44    4869 2042.48  4929.5 2034.17  4962.2  2032.6  4966.7 2029.54
  4967.7 2029.04  5013.2 2029.54  5013.6 2031.75  5029.2 2033.62  5050.6  2033.8
  5066.2 2035.41  5103.2 2042.32    5109 2042.22  5124.6 2049.07  5130.4 2048.31
  5151.9 2054.88  5243.7 2057.23  5379.6 2058.85  5459.4 2061.91  5682.7 2061.62
#Mann= 5 ,-1 , 0
  4596.9     .07       0  4855.1    .035       0  4966.7    .035       0
  5013.2    .035       0  5243.7     .07       0
Bank Sta=4966.7,5013.2
XS Rating Curve= 0 ,0
Exp/Cntr=0.3,0.1

Type RM Length L Ch R = 1 ,94856   ,567,567,567
BEGIN DESCRIPTION:
South Fork Guadalupe River 142.0
END DESCRIPTION:
XS GIS Cut Line= 3
      1819425.04     13897824.99        1819825.       13897775.
      1820222.56     13897082.24
#Sta/Elev= 30
  4608.5 2094.44  4668.9 2090.72  4749.5 2080.96  4850.3 2071.62  4870.5 2067.65
  4879.9 2059.18  4888.1 2049.42  4893.2 2040.92  4900.8 2035.98  4930.9 2029.35
    4941 2028.22  4945.4  2025.7  4946.4  2025.2    4992  2025.7  5001.5  2028.3
  5034.6  2029.9  5046.8 2032.44  5078.4 2035.29  5105.8 2036.88  5115.3 2036.31
  5121.6 2038.55  5127.4 2037.73  5149.9 2041.16  5202.1  2046.4  5325.9 2051.35
  5422.2 2055.04  5472.8 2054.04  5502.8 2055.07  5757.3  2058.2  5810.3 2059.39
#Mann= 8 ,-1 , 0
  4608.5      .1       0  4879.9     .07       0  4900.8      .1       0
  4945.4     .05       0    4992      .1       0  5325.9    .035       0
  5502.8      .1       0  5757.3     .07       0
Bank Sta=4945.4,4992
XS Rating Curve= 0 ,0
Exp/Cntr=0.3,0.1

Type RM Length L Ch R = 1 ,94289   ,541,541,541
BEGIN DESCRIPTION:
South Fork Guadalupe River 141.0
END DESCRIPTION:
XS GIS Cut Line= 3
      1820725.03     13898175.02        1820325.       13897925.
      1820239.79     13897146.59
#Sta/Elev= 30
  4528.3  2102.2    4615  2096.8  4630.3 2093.27  4651.6 2092.54  4666.9 2088.54
  4672.8 2089.12  4688.1 2084.37  4709.4 2083.78  4724.7 2079.73  4803.7 2073.96
    4819 2069.77  4840.2 2068.31  4892.1 2055.07  4905.7 2055.38  4913.4 2047.17
  4919.3 2037.47  4934.6 2029.33  4949.9 2026.56  4955.8 2023.39  4971.1 2025.97
  4986.6 2021.41  4987.6 2020.91  5033.5 2021.41  5045.6 2027.54  5150.9 2040.49
  5251.5 2046.44  5419.2 2051.53  5606.1 2054.11  5716.4 2056.44  5783.1 2057.55
#Mann= 6 ,-1 , 0
  4528.3      .1       0  4986.6     .05       0  5033.5      .1       0
  5419.2    .035       0  5606.1      .1       0  5716.4     .07       0
Bank Sta=4986.6,5033.5
XS Rating Curve= 0 ,0
Exp/Cntr=0.3,0.1

Type RM Length L Ch R = 1 ,93748   ,554,554,554
BEGIN DESCRIPTION:
South Fork Guadalupe River 140.0
END DESCRIPTION:
XS GIS Cut Line= 3
      1821125.01       13897925.        1820775.       13897725.
      1820339.65     13897263.18
#Sta/Elev= 30
  4596.9 2151.35  4632.2 2148.81  4728.6 2145.39  4750.2 2143.07  4787.7 2135.67
  4809.3 2134.35  4868.3 2123.25  4911.5 2117.28  4927.3 2113.12  4933.1 2097.58
  4942.4    2082  4948.9 2076.94  4954.7 2068.61  4964.8 2032.66  4970.5 2018.27
  4983.7 2010.87  4984.7 2010.37  5030.6 2010.87  5035.4    2015  5063.7 2021.76
  5098.9 2034.77  5113.1 2037.95    5177 2041.83  5294.3 2045.12    5389 2048.89
  5431.5 2050.01  5467.1 2049.18  5509.2 2051.65  5578.6 2053.13  5634.7 2054.92
#Mann= 5 ,-1 , 0
  4596.9      .1       0  4983.7     .05       0  5030.6      .1       0
  5294.3    .035       0  5578.6      .1       0
Bank Sta=4983.7,5030.6
XS Rating Curve= 0 ,0
Exp/Cntr=0.3,0.1

Type RM Length L Ch R = 1 ,93194   ,550,550,550
BEGIN DESCRIPTION:
South Fork Guadalupe River 139.0
END DESCRIPTION:
XS GIS Cut Line= 3
        1821175.     13897674.99        1821075.       13897275.
      1820875.01     13896925.01
#Sta/Elev= 30
  4596.6 2113.65  4697.1 2102.29  4702.2 2103.56  4738.3 2098.08  4743.5  2099.2
  4761.5 2095.05  4771.8 2091.72  4792.4 2081.65  4825.9 2070.84  4854.3  2058.1
  4885.2 2039.65  4908.4 2029.31  4926.1 2023.09  4927.1 2022.59  4973.1 2023.09
  4990.9  2025.2  5022.6 2025.32  5031.9 2023.78    5060 2026.36  5097.4 2026.16
  5177.9 2029.41  5193.2 2031.22  5225.8 2040.39  5242.8 2044.13  5280.3 2046.67
  5301.9 2049.68  5317.7 2049.27  5323.5 2050.75  5339.3 2050.51    5412 2054.87
#Mann= 5 ,-1 , 0
  4596.6      .1       0  4926.1    .035       0  4973.1      .1       0
  5177.9      .1       0  5225.8     .07       0
Bank Sta=4926.1,4973.1
XS Rating Curve= 0 ,0
Exp/Cntr=0.3,0.1

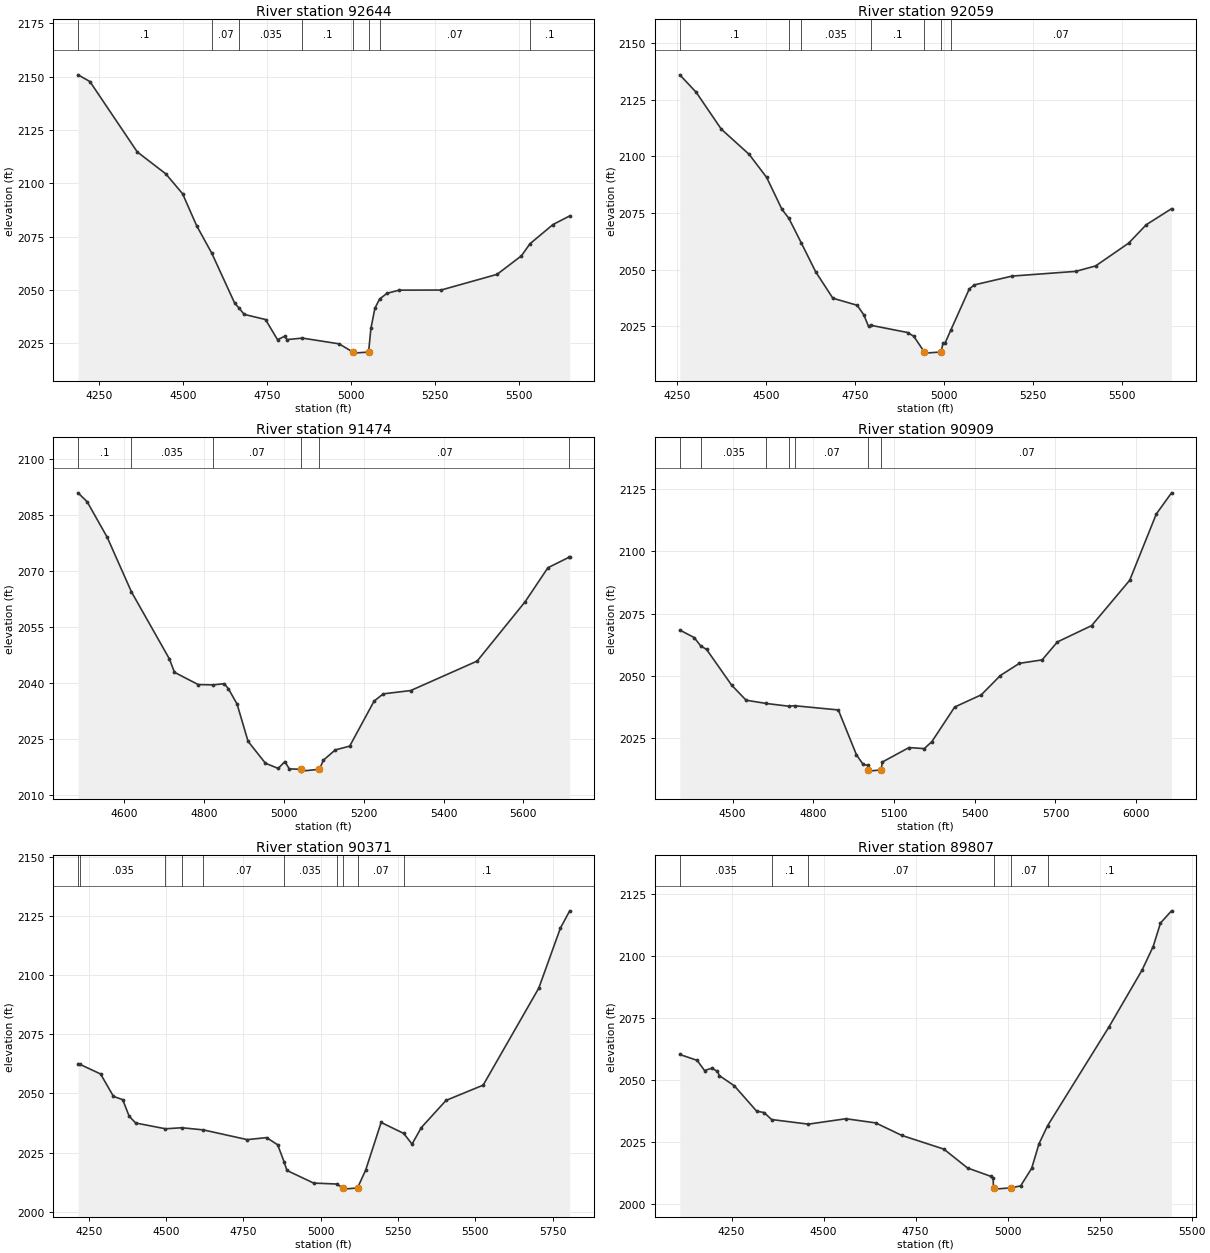
Type RM Length L Ch R = 1 ,92644   ,585,585,585
BEGIN DESCRIPTION:
South Fork Guadalupe River 138.0
END DESCRIPTION:
XS GIS Cut Line= 3
      1821875.03     13897425.03        1821325.       13896825.
        1820975.       13896275.
#Sta/Elev= 30
    4186 2150.84  4221.5 2147.69  4362.7 2114.69  4447.8  2104.4  4497.7 2095.11
  4539.7 2080.11  4584.8  2067.2  4653.1 2043.79  4666.3 2041.44  4681.5 2038.52
    4745 2036.11  4780.8 2026.65  4801.7 2028.22  4809.1 2026.69    4855  2027.4
  4964.5  2024.7  5005.3 2020.85  5006.3 2020.35  5052.3 2020.85  5059.2  2031.9
  5071.1 2041.38    5085 2045.71  5107.5 2048.43  5143.9 2049.88  5268.4 2049.93
  5435.2 2057.28    5508 2065.98  5533.2  2071.6  5601.9 2080.63  5651.9 2084.69
#Mann= 8 ,-1 , 0
    4186      .1       0  4584.8     .07       0  4666.3    .035       0
    4855      .1       0  5005.3     .05       0  5052.3      .1       0
    5085     .07       0  5533.2      .1       0
Bank Sta=5005.3,5052.3
XS Rating Curve= 0 ,0
Exp/Cntr=0.3,0.1

Type RM Length L Ch R = 1 ,92059   ,585,585,585
BEGIN DESCRIPTION:
South Fork Guadalupe River 137.0
END DESCRIPTION:
XS GIS Cut Line= 3
      1822025.01     13897175.03        1821775.       13896475.
      1821275.04     13896075.03
#Sta/Elev= 30
  4256.9 2136.07  4303.1 2128.33  4373.7 2112.05  4451.8 2100.96  4501.2 2090.75
  4544.2 2076.68  4563.9 2072.62  4598.5 2061.87  4639.2 2049.04  4687.5 2037.38
    4756 2034.25  4774.6 2030.03  4787.9 2024.94  4795.3 2025.39  4897.8 2022.22
  4915.3 2020.54  4944.9 2013.61  4945.9 2013.11  4991.9 2013.61  4997.6 2017.59
  5003.4 2017.59  5019.3 2023.24  5071.5  2041.5  5085.9 2043.27  5192.3 2047.16
  5370.8 2049.23  5426.8 2051.63  5519.7 2061.69  5569.3 2069.83  5640.5 2076.92
#Mann= 7 ,-1 , 0
  4256.9      .1       0  4563.9     .07       0  4598.5    .035       0
  4795.3      .1       0  4944.9     .05       0  4991.9      .1       0
  5019.3     .07       0
Bank Sta=4944.9,4991.9
XS Rating Curve= 0 ,0
Exp/Cntr=0.3,0.1

Type RM Length L Ch R = 1 ,91474   ,565,565,565
BEGIN DESCRIPTION:
South Fork Guadalupe River 136.0
END DESCRIPTION:
XS GIS Cut Line= 3
      1822475.02     13896575.03        1822225.       13896125.
      1821575.01       13895825.
#Sta/Elev= 30
  4485.2    2091  4508.1 2088.61  4558.4 2079.05    4619 2064.41    4714 2046.41
  4726.6 2042.83  4786.1 2039.53  4823.6 2039.45  4851.3 2039.78  4861.6 2038.42
  4883.3 2034.31  4910.8 2024.31  4954.3 2018.42  4986.3 2017.03  5002.8 2018.85
  5014.2  2016.9  5042.5  2016.8  5043.5  2016.3  5089.6  2016.8  5099.1 2019.21
    5129 2021.99  5165.2 2023.01  5226.3  2035.1  5249.2 2037.04    5318 2037.93
  5484.2 2045.84  5604.4 2061.78  5661.3 2070.89  5714.8 2073.74  5715.9 2073.74
#Mann= 6 ,-1 , 0
  4485.2      .1       0    4619    .035       0  4823.6     .07       0
  5042.5     .05       0  5089.6     .07       0  5714.8    .035       0
Bank Sta=5042.5,5089.6
XS Rating Curve= 0 ,0
Exp/Cntr=0.3,0.1

Type RM Length L Ch R = 1 ,90909   ,538,538,538
BEGIN DESCRIPTION:
South Fork Guadalupe River 135.0
END DESCRIPTION:
XS GIS Cut Line= 3
      1822774.99     13896324.97        1822525.       13895675.
      1821724.97     13894874.97
#Sta/Elev= 30
  4303.6 2068.39  4357.1 2065.38  4380.9 2062.05  4403.2 2060.58  4496.4 2046.22
    4550 2040.19  4625.3 2038.87  4708.3 2037.77    4730 2037.97  4892.8 2036.27
  4960.3 2018.21    4985 2014.39  5003.5 2013.96  5004.7 2012.17  5005.7 2011.67
  5051.8 2012.17  5056.6 2015.34  5155.6 2021.15  5212.1 2020.72  5240.4 2023.51
  5325.3 2037.44  5424.3 2042.36    5495  2050.1  5565.7 2055.01  5650.5  2056.4
  5707.1 2063.62  5834.4 2070.18  5975.8 2088.39  6074.8 2115.06  6131.4 2123.57
#Mann= 7 ,-1 , 0
  4303.6      .1       0  4380.9    .035       0  4625.3     .07       0
  4708.3      .1       0    4730     .07       0  5004.7     .05       0
  5051.8     .07       0
Bank Sta=5004.7,5051.8
XS Rating Curve= 0 ,0
Exp/Cntr=0.3,0.1

Type RM Length L Ch R = 1 ,90371   ,564,564,564
BEGIN DESCRIPTION:
South Fork Guadalupe River 134.0
END DESCRIPTION:
XS GIS Cut Line= 3
      1823224.99     13895874.98        1822775.       13895225.
        1822775.     13894425.05
#Sta/Elev= 30
  4215.1 2062.53  4220.2 2062.38  4288.1 2058.24  4329.9 2048.75  4359.7 2047.39
  4380.6 2040.38  4401.6 2037.53  4498.1 2035.08    4551 2035.52  4620.5 2034.61
  4762.4  2030.5  4825.2 2031.35    4861 2028.31  4881.8  2021.1  4890.8 2017.48
  4977.3 2012.14  5051.7 2011.74    5072 2010.08    5073 2009.58  5119.2 2010.08
  5145.6 2017.62  5195.6 2037.76  5268.5 2033.13  5295.6 2028.62  5325.6 2035.59
  5405.6 2047.08  5525.6 2053.52  5705.6 2094.54  5775.6 2119.92  5805.6 2127.18
#Mann= 10 ,-1 , 0
  4215.1     .07       0  4220.2    .035       0  4498.1     .07       0
    4551      .1       0  4620.5     .07       0  4881.8    .035       0
  5051.7     .07       0    5072    .035       0  5119.2     .07       0
  5268.5      .1       0
Bank Sta=5072,5119.2
XS Rating Curve= 0 ,0
Exp/Cntr=0.3,0.1

Type RM Length L Ch R = 1 ,89807   ,544,544,544
BEGIN DESCRIPTION:
South Fork Guadalupe River 133.0
END DESCRIPTION:
XS GIS Cut Line= 3
       1823304.9     13895801.47        1823175.       13894925.
        1823175.     13894475.05
#Sta/Elev= 30
  4109.3 2060.14  4156.3 2057.77  4176.5 2053.67  4196.7 2054.62  4211.4 2053.32
  4216.9  2051.6  4257.4  2047.5    4318 2037.29  4338.2 2036.71  4358.7 2033.89
  4458.6 2032.04  4560.6 2034.22  4641.5 2032.54  4712.3  2027.5  4826.7 2021.96
  4891.1 2014.35  4954.9 2010.94  4960.6 2010.19  4961.6 2006.32  4962.6 2005.82
  5008.8 2006.32  5035.3 2007.13  5065.3 2014.21  5085.3 2024.15  5108.5  2031.4
  5275.3 2071.25  5365.3 2094.21  5395.3 2103.65  5415.3 2113.17  5445.3 2118.09
#Mann= 6 ,-1 , 0
  4109.3    .035       0  4358.7      .1       0  4458.6     .07       0
  4961.6     .05       0  5008.8     .07       0  5108.5      .1       0
Bank Sta=4961.6,5008.8
XS Rating Curve= 0 ,0
Exp/Cntr=0.3,0.1

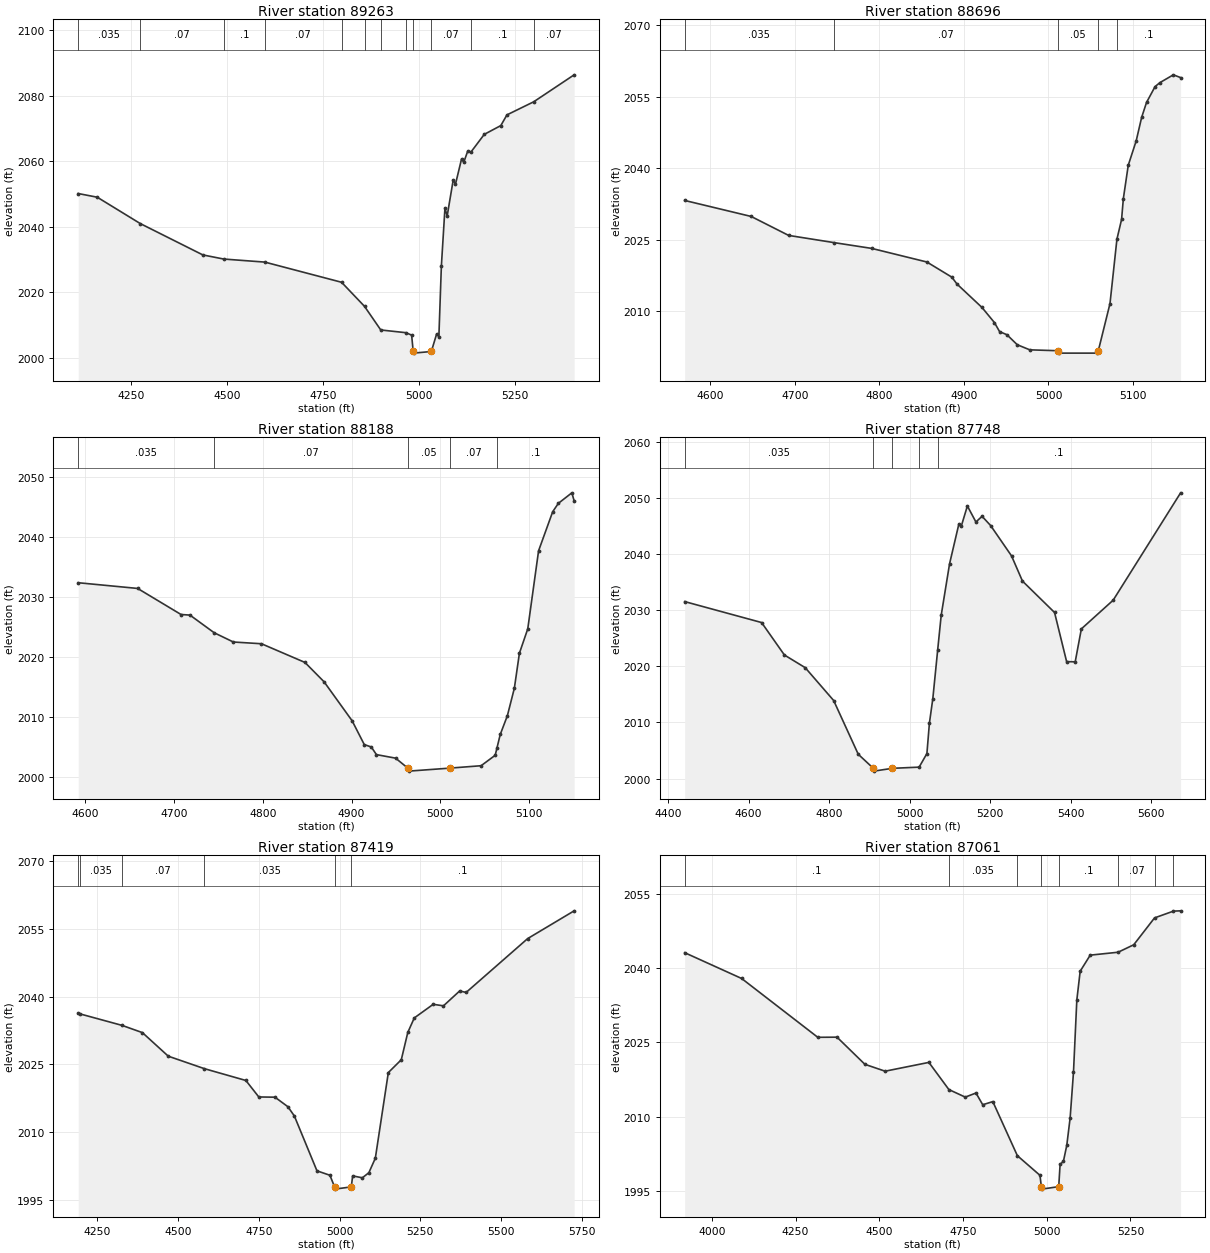
Type RM Length L Ch R = 1 ,89263   ,567,567,567
BEGIN DESCRIPTION:
South Fork Guadalupe River 132.0
END DESCRIPTION:
XS GIS Cut Line= 3
      1823492.45     13895743.41        1823675.       13894875.
        1823475.     13894525.01
#Sta/Elev= 30
  4112.5 2050.21    4162 2049.09    4274 2041.04  4436.8 2031.47  4491.2 2030.21
  4598.1 2029.28  4797.8 2023.12  4857.5 2015.77  4899.8 2008.56  4965.2 2007.73
  4980.1 2006.99  4984.2 2001.99  4985.2 2001.49  5031.4 2001.99  5045.2 2007.36
    5051 2006.55  5057.5 2028.09  5066.8 2045.75  5072.6 2043.38  5088.4 2054.42
  5094.2 2053.06    5110 2060.76  5115.8 2059.77  5125.9 2063.11  5134.8 2062.93
  5169.1 2068.27  5212.2 2070.96  5228.1 2074.22  5297.8 2078.22    5403 2086.45
#Mann= 12 ,-1 , 0
  4112.5    .035       0    4274     .07       0  4491.2      .1       0
  4598.1     .07       0  4797.8    .035       0  4857.5     .07       0
  4899.8    .035       0  4965.2     .07       0  4984.2     .05       0
  5031.4     .07       0  5134.8      .1       0  5297.8     .07       0
Bank Sta=4984.2,5031.4
XS Rating Curve= 0 ,0
Exp/Cntr=0.3,0.1

Type RM Length L Ch R = 1 ,88696   ,508,508,508
BEGIN DESCRIPTION:
South Fork Guadalupe River 131.0
END DESCRIPTION:
XS GIS Cut Line= 3
      1823875.01     13895524.99        1824125.       13895175.
       1824202.5     13895039.38
#Sta/Elev= 30
  4569.9 2033.25  4648.5 2029.89  4692.8 2025.91  4746.1 2024.41  4791.1 2023.18
  4856.2 2020.33  4885.7 2017.15  4891.9 2015.69  4921.4 2010.78  4936.1 2007.61
  4942.2 2005.71  4950.8 2005.07  4963.1 2002.96  4977.9 2001.89  5011.6  2001.7
  5012.6  2001.2  5057.9  2001.2  5058.9  2001.7  5072.7  2011.6  5080.9 2025.11
  5086.4 2029.26  5088.5 2033.64  5094.3 2040.64  5103.7 2045.77  5110.1 2050.67
  5115.9 2053.82    5126 2057.15  5131.7 2057.98  5147.6 2059.62  5156.2 2059.04
#Mann= 5 ,-1 , 0
  4569.9    .035       0  4746.1     .07       0  5011.6     .05       0
  5058.9     .07       0  5080.9      .1       0
Bank Sta=5011.6,5058.9
XS Rating Curve= 0 ,0
Exp/Cntr=0.3,0.1

Type RM Length L Ch R = 1 ,88188   ,440,440,440
BEGIN DESCRIPTION:
South Fork Guadalupe River 130.0
END DESCRIPTION:
XS GIS Cut Line= 3
      1824074.98     13895725.01        1824425.       13895525.
      1824502.38     13895389.59
#Sta/Elev= 30
  4591.8 2032.42  4658.8 2031.47  4707.7 2027.13  4717.8 2027.03  4745.1 2024.09
  4766.7 2022.55  4798.4 2022.26  4847.4 2019.15    4869 2015.92  4900.6 2009.43
  4914.3 2005.47  4922.2 2005.07    4928  2003.8  4949.6 2003.21  4963.4 2001.55
  4964.4 2001.05  5010.7 2001.55    5046 2001.95  5061.9 2003.69  5063.8 2004.85
  5067.6 2007.16  5075.6 2010.27  5083.5 2014.86  5089.2 2020.69  5098.6 2024.74
  5110.8 2037.74  5126.7 2044.24  5133.1 2045.64  5148.3 2047.39  5150.9 2046.05
#Mann= 5 ,-1 , 0
  4591.8    .035       0  4745.1     .07       0  4963.4     .05       0
  5010.7     .07       0  5063.8      .1       0
Bank Sta=4963.4,5010.7
XS Rating Curve= 0 ,0
Exp/Cntr=0.3,0.1

Type RM Length L Ch R = 1 ,87748   ,329,329,329
BEGIN DESCRIPTION:
South Fork Guadalupe River 129.1
END DESCRIPTION:
XS GIS Cut Line= 4
      1824131.86     13895946.34      1824639.48     13895847.56
      1824746.85     13895702.48      1825029.55     13895249.36
#Sta/Elev= 30
  4441.2 2031.52  4632.2 2027.79  4688.9 2022.01  4740.5 2019.76  4811.2 2013.91
  4872.3 2004.34  4909.8 2001.84  4910.8 2001.34  4957.1 2001.84  5023.5 2002.05
  5042.8 2004.47    5049 2009.88  5057.5 2014.25  5069.6 2022.95  5078.3 2029.09
  5099.1 2038.26  5122.2 2045.34  5128.4    2045  5143.3 2048.54  5164.5 2045.69
  5179.8  2046.7  5201.1 2045.05    5253 2039.65  5280.1 2035.17  5359.8 2029.58
  5389.8 2020.83  5411.1  2020.8  5426.4 2026.66  5505.4 2031.77  5672.9 2050.88
#Mann= 5 ,-1 , 0
  4441.2    .035       0  4909.8    .035       0  4957.1    .035       0
  5023.5     .07       0  5069.6      .1       0
Bank Sta=4909.8,4957.1
XS Rating Curve= 0 ,0
Exp/Cntr=0.3,0.1

Type RM Length L Ch R = 1 ,87419   ,358,358,358
BEGIN DESCRIPTION:
South Fork Guadalupe River 129.0
END DESCRIPTION:
XS GIS Cut Line= 4
      1823966.46     13896131.05      1824729.38     13896109.01
        1825125.       13896075.      1825498.71      13896054.3
#Sta/Elev= 30
  4191.3 2036.29  4195.5 2036.22    4327 2033.65  4389.9 2032.05    4470 2026.83
    4582 2024.06  4710.1 2021.45  4750.1  2017.8  4800.1 2017.75  4840.1 2015.64
  4860.1 2013.59  4930.1 2001.44  4970.2 2000.46  4984.5 1997.89  4985.5 1997.39
  5036.3 1997.89  5040.5 2000.32  5070.6  1999.9  5090.7 2001.03  5110.7 2004.24
  5150.9  2023.2    5191 2026.04  5211.1 2032.08  5231.2  2035.3  5289.8 2038.32
  5321.5 2037.98  5371.6 2041.27  5391.7 2040.95    5582 2052.87  5725.9 2059.02
#Mann= 6 ,-1 , 0
  4191.3     .07       0  4195.5    .035       0    4327     .07       0
    4582    .035       0  4984.5    .035       0  5036.3      .1       0
Bank Sta=4984.5,5036.3
XS Rating Curve= 0 ,0
Exp/Cntr=0.3,0.1

Type RM Length L Ch R = 1 ,87061   ,578,578,578
BEGIN DESCRIPTION:
South Fork Guadalupe River 128.0
END DESCRIPTION:
XS GIS Cut Line= 3
       1823799.6     13896537.61        1824875.       13896425.
      1825275.02       13896425.
#Sta/Elev= 30
  3918.7 2043.14  4088.9 2037.92  4316.3 2026.03  4373.7 2026.06    4457 2020.57
  4517.4 2019.18  4648.1 2020.96  4707.8 2015.47  4756.8 2013.94  4788.8 2014.77
  4808.9  2012.4  4839.1 2013.03  4912.4  2002.1  4979.9 1998.13    4984 1995.84
    4985 1995.34  5035.9 1995.84    5040 2000.32    5050 2000.98    5060  2004.2
    5070 2009.73    5080 2018.96    5090 2033.58    5100 2039.39    5130 2042.64
  5213.3 2043.23    5260 2044.74  5322.1 2050.17  5378.6 2051.54    5400  2051.6
#Mann= 8 ,-1 , 0
  3918.7      .1       0  4707.8    .035       0  4912.4      .1       0
    4984     .05       0  5035.9      .1       0  5213.3     .07       0
  5322.1      .1       0  5378.6     .07       0
Bank Sta=4984,5035.9
XS Rating Curve= 0 ,0
Exp/Cntr=0.3,0.1

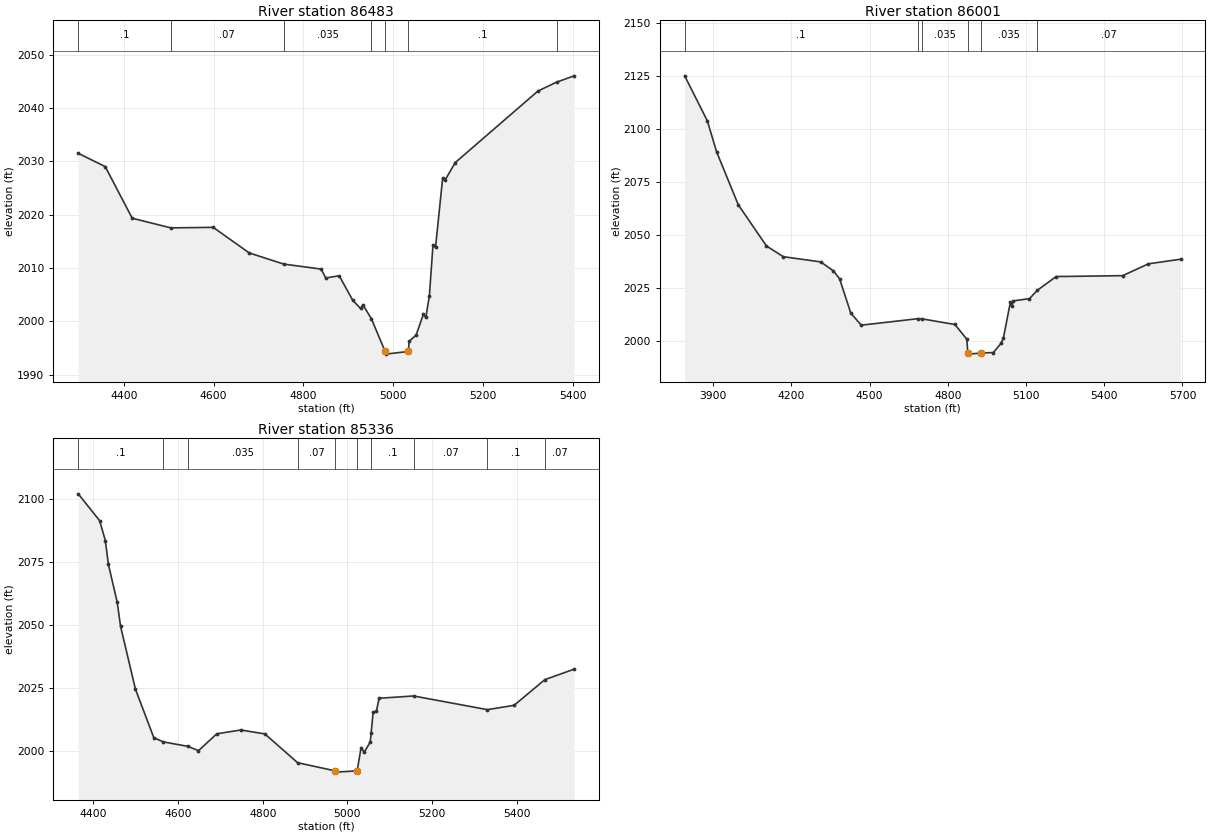
Type RM Length L Ch R = 1 ,86483   ,482,482,482
BEGIN DESCRIPTION:
South Fork Guadalupe River 127.0
END DESCRIPTION:
XS GIS Cut Line= 3
      1824174.96       13896925.        1824875.       13896975.
      1825224.97     13896775.02
#Sta/Elev= 30
  4298.2 2031.53  4358.4 2029.03  4418.5 2019.35  4504.6 2017.54    4599 2017.64
  4679.2 2012.84  4756.1 2010.75  4839.6 2009.81  4849.6 2008.14  4879.7 2008.56
  4909.8 2003.96  4927.3 2002.42  4932.4 2003.12  4951.2 2000.53    4982 1994.36
    4983 1993.86  5033.9 1994.36  5035.3 1996.24  5051.1 1997.45    5067  2001.3
  5072.7 2000.75  5080.6 2004.82  5088.6 2014.34  5094.3  2013.9  5110.2 2026.94
  5115.9 2026.55  5138.2 2029.79  5322.5 2043.21  5364.2 2044.88  5403.1 2046.06
#Mann= 7 ,-1 , 0
  4298.2      .1       0  4504.6     .07       0  4756.1    .035       0
  4951.2      .1       0    4982     .05       0  5033.9      .1       0
  5364.2     .07       0
Bank Sta=4982,5033.9
XS Rating Curve= 0 ,0
Exp/Cntr=0.3,0.1

Type RM Length L Ch R = 1 ,86001   ,665,665,665
BEGIN DESCRIPTION:
South Fork Guadalupe River 126.0
END DESCRIPTION:
XS GIS Cut Line= 3
      1823804.53     13897895.09      1824937.35     13897436.32
      1825601.91     13897294.56
#Sta/Elev= 30
  3791.1 2125.04  3877.9 2103.84  3913.4 2089.28  3996.6 2064.29  4104.5 2044.92
  4169.2 2039.83  4312.8 2037.38  4361.1 2033.16    4385 2029.45  4428.1 2013.25
  4468.3 2007.57  4684.7 2010.62  4700.5 2010.56  4827.3 2007.89  4873.1 2000.94
  4876.9 1994.43  4877.9 1993.93  4928.8 1994.43  4974.9 1994.69  5004.4 1999.07
  5013.3 2001.56    5040 2018.41  5045.1 2016.44  5051.8 2019.04  5113.1 2020.06
  5143.8 2024.05  5215.4 2030.47  5470.4  2030.9  5569.5 2036.47  5692.8 2038.65
#Mann= 6 ,-1 , 0
  3791.1      .1       0  4684.7     .07       0  4700.5    .035       0
  4876.9     .05       0  4928.8    .035       0  5143.8     .07       0
Bank Sta=4876.9,4928.8
XS Rating Curve= 0 ,0
Exp/Cntr=0.3,0.1

Type RM Length L Ch R = 1 ,85336   ,559,559,559
BEGIN DESCRIPTION:
South Fork Guadalupe River 125.0
END DESCRIPTION:
XS GIS Cut Line= 3
      1824424.96     13898375.03        1824925.       13897975.
      1825275.02     13897574.97
#Sta/Elev= 30
    4364 2102.09  4414.5 2091.47  4428.1 2083.55  4435.3 2074.09  4456.1 2059.12
  4464.1 2049.46  4499.3 2024.52  4542.5 2005.36  4564.2 2003.66  4623.2 2001.84
  4648.2 2000.14  4691.4 2006.83  4748.2 2008.35  4805.1 2006.78  4882.4 1995.36
  4971.2 1992.12  4972.2 1991.62  5023.1 1992.12  5032.4  2001.3  5039.9 1999.54
  5054.2 2003.62  5056.2 2007.16  5060.8 2015.31  5068.4 2015.69  5075.1 2020.94
  5156.4 2021.85  5330.9 2016.42    5394 2018.14  5466.7 2028.34  5535.9 2032.49
#Mann= 10 ,-1 , 0
    4364      .1       0  4564.2     .07       0  4623.2    .035       0
  4882.4     .07       0  4971.2     .05       0  5023.1     .07       0
  5056.2      .1       0  5156.4     .07       0  5330.9      .1       0
  5466.7     .07       0
Bank Sta=4971.2,5023.1
XS Rating Curve= 0 ,0
Exp/Cntr=0.3,0.1