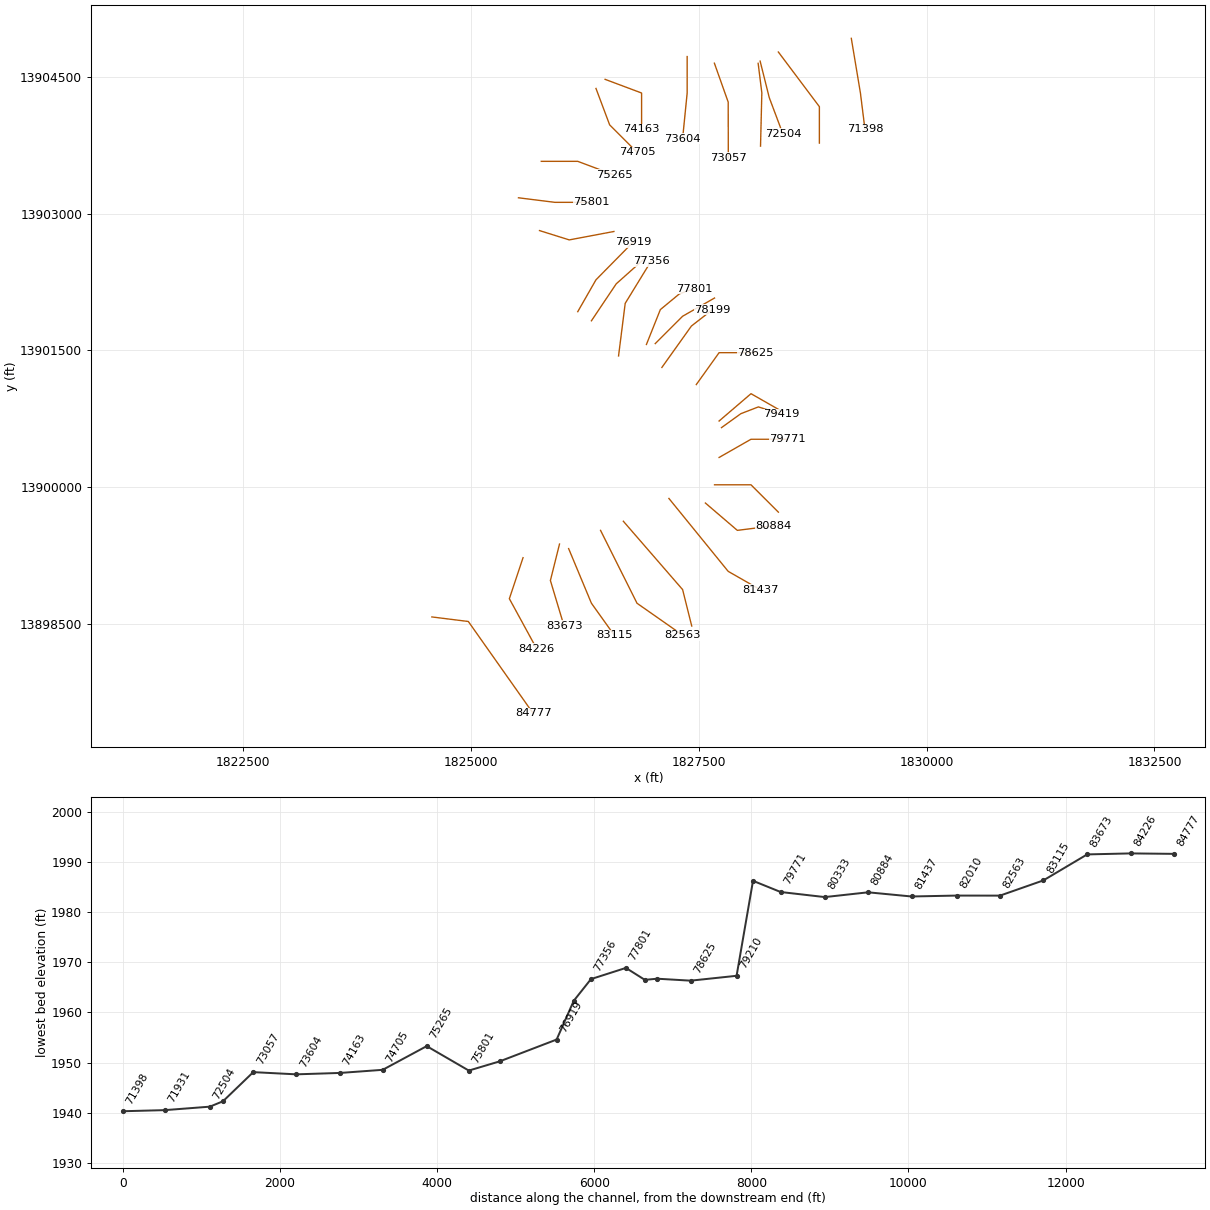
HEC-RAS study South Fork Guadalupe River.prj: South Fork Guadalupe River Base Level Engineering

--- South Fork Guadalupe River.g01 (geometry) --- (continued)

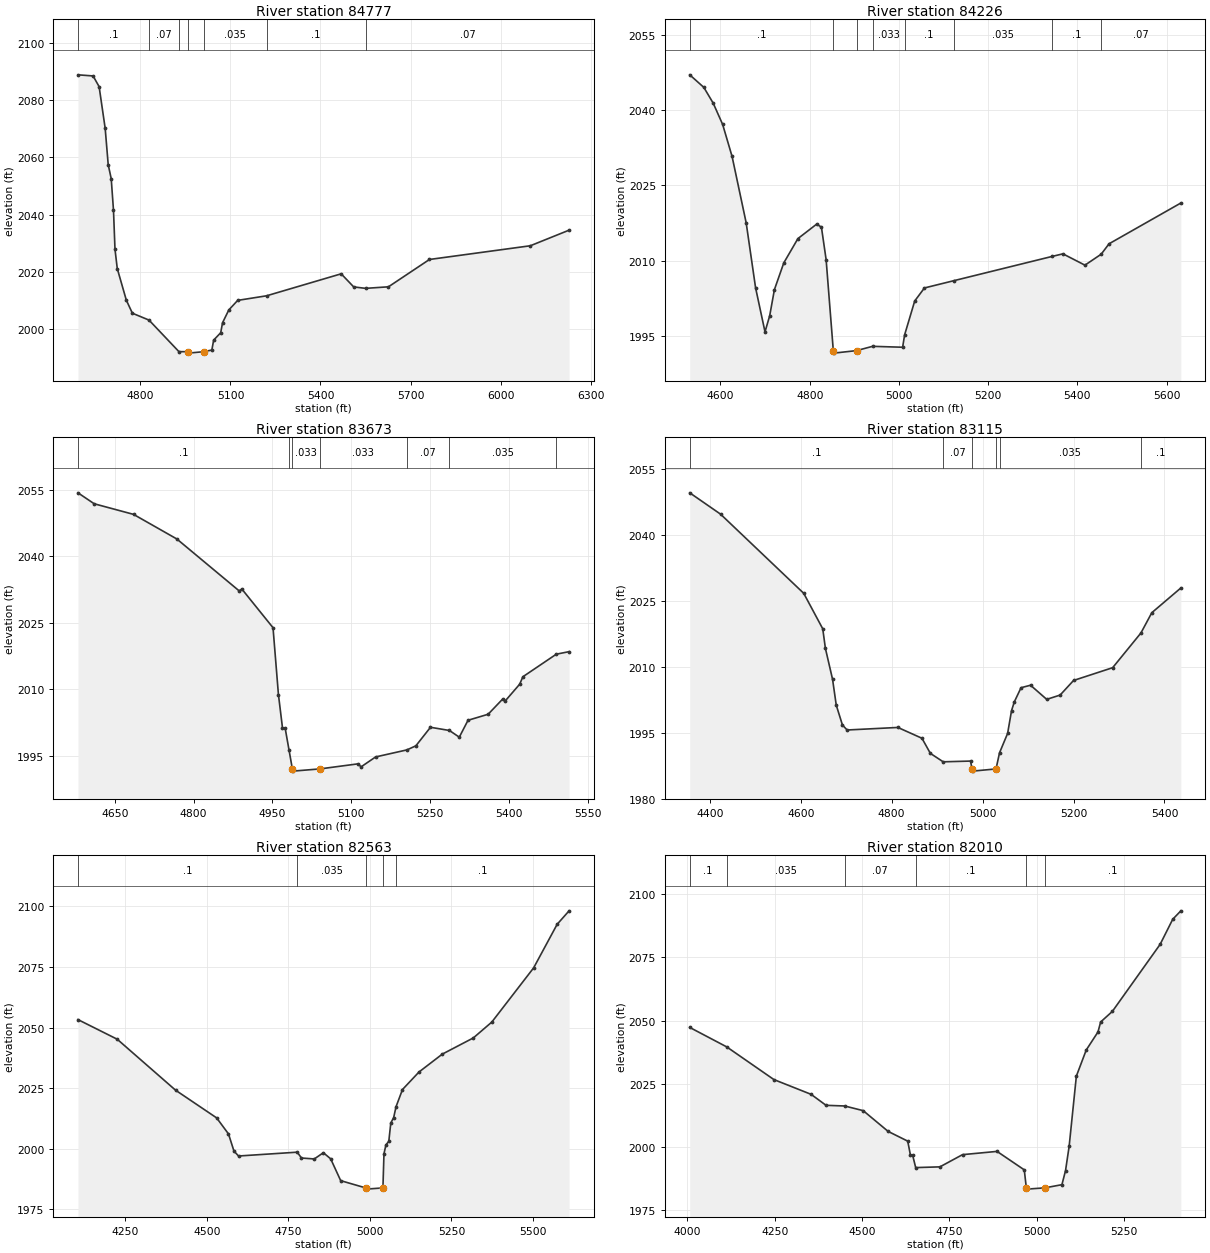
Type RM Length L Ch R = 1 ,84777   ,551,551,551
BEGIN DESCRIPTION:
South Fork Guadalupe River 124.0
END DESCRIPTION:
XS GIS Cut Line= 3
      1824575.01       13898575.        1824975.       13898525.
      1825685.92     13897516.48
#Sta/Elev= 30
  4591.6 2088.83    4642 2088.44  4662.1  2084.7  4682.3 2070.13  4692.4 2057.43
  4702.4 2052.56    4710 2041.51    4715 2027.86  4722.6 2021.14  4752.8 2010.09
    4773 2005.54  4828.4 2003.14  4928.1 1992.12  4958.6  1992.1  4959.6  1991.6
  5010.6  1992.1  5037.8 1992.67  5043.9 1996.15  5067.4 1998.73  5073.5 2002.21
  5094.4 2006.69    5124 2010.03  5220.3 2011.63  5468.9 2019.31  5510.7 2014.73
  5550.5 2014.23  5626.5 2014.77  5763.2 2024.32  6099.4 2029.11  6228.6 2034.56
#Mann= 7 ,-1 , 0
  4591.6      .1       0  4828.4     .07       0  4928.1    .035       0
  4958.6    .035       0  5010.6    .035       0  5220.3      .1       0
  5550.5     .07       0
Bank Sta=4958.6,5010.6
XS Rating Curve= 0 ,0
Exp/Cntr=0.3,0.1

Type RM Length L Ch R = 1 ,84226   ,553,553,553
BEGIN DESCRIPTION:
South Fork Guadalupe River 123.0
END DESCRIPTION:
XS GIS Cut Line= 3
      1825575.01     13899225.02        1825425.       13898775.
      1825725.02     13898224.97
#Sta/Elev= 30
  4531.1 2046.99  4562.7 2044.49  4583.8 2041.34  4604.9 2037.12    4626 2030.77
  4657.6 2017.58  4678.7 2004.66  4699.8 1995.92  4710.3 1999.11  4720.9 2004.31
  4741.9 2009.62  4773.6 2014.45  4815.7 2017.33  4826.3 2016.71  4836.8 2010.28
  4852.9 1992.19    4854 1991.69    4905 1992.19  4940.9 1993.04  5008.3 1992.86
  5012.8 1995.33  5035.4 2002.05  5057.2 2004.64  5122.9 2006.08  5343.1  2010.9
  5367.6 2011.42    5417 2009.17  5453.3 2011.34  5471.1 2013.42    5632 2021.52
#Mann= 8 ,-1 , 0
  4531.1      .1       0  4852.9    .033       0    4905      .1       0
  4940.9    .033       0  5012.8      .1       0  5122.9    .035       0
  5343.1      .1       0  5453.3     .07       0
Bank Sta=4852.9,4905
XS Rating Curve= 0 ,0
Exp/Cntr=0.3,0.1

Type RM Length L Ch R = 1 ,83673   ,558,558,558
BEGIN DESCRIPTION:
South Fork Guadalupe River 122.0
END DESCRIPTION:
XS GIS Cut Line= 3
      1825975.01     13899375.03        1825875.       13898975.
      1826025.01     13898474.95
#Sta/Elev= 30
  4580.1 2054.27    4611  2051.8  4685.8 2049.41  4768.2 2043.86  4886.8 2032.15
  4891.9 2032.57  4951.2 2023.84  4961.5 2008.76  4969.2 2001.27  4974.4 2001.11
  4981.6 1996.29    4988 1991.99    4989 1991.49  5040.4 1991.99  5113.4 1993.14
  5118.6 1992.44  5146.4 1994.69    5206 1996.28    5223  1997.2  5250.8 2001.38
  5286.8 2000.66  5305.6 1999.15  5322.2 2002.96  5360.5 2004.32  5388.3 2007.77
  5393.5 2007.39  5420.5  2011.1  5426.6 2012.78  5490.2 2017.87  5514.5 2018.44
#Mann= 7 ,-1 , 0
  4580.1      .1       0  4981.6    .033       0    4988    .033       0
  5040.4    .033       0    5206     .07       0  5286.8    .035       0
  5490.2     .07       0
Bank Sta=4988,5040.4
XS Rating Curve= 0 ,0
Exp/Cntr=0.3,0.1

Type RM Length L Ch R = 1 ,83115   ,552,552,552
BEGIN DESCRIPTION:
South Fork Guadalupe River 121.0
END DESCRIPTION:
XS GIS Cut Line= 3
      1826075.02     13899324.96        1826325.       13898725.
      1826575.02     13898374.97
#Sta/Elev= 30
  4355.9 2049.64  4423.6 2044.79  4606.6 2026.77  4648.4  2018.7  4654.3 2014.22
    4670  2007.2  4678.1 2001.33  4691.7 1996.81    4702 1995.67  4813.6 1996.25
  4866.6 1993.79  4885.1 1990.35  4913.3 1988.43  4973.4  1988.6  4976.8 1986.81
  4977.8 1986.31  5029.5 1986.81  5037.2 1990.48    5055  1994.9  5063.6 2000.07
  5069.8 2002.09  5084.5 2005.29  5105.4 2005.86    5141 2002.64  5170.5 2003.62
    5200 2006.94    5286 2009.85  5348.2 2017.75  5372.1 2022.36    5436 2027.99
#Mann= 6 ,-1 , 0
  4355.9      .1       0  4913.3     .07       0  4976.8     .05       0
  5029.5     .07       0  5037.2    .035       0  5348.2      .1       0
Bank Sta=4976.8,5029.5
XS Rating Curve= 0 ,0
Exp/Cntr=0.3,0.1

Type RM Length L Ch R = 1 ,82563   ,553,553,553
BEGIN DESCRIPTION:
South Fork Guadalupe River 120.0
END DESCRIPTION:
XS GIS Cut Line= 3
      1826424.99     13899525.03        1826825.       13898725.
      1827325.01     13898374.99
#Sta/Elev= 30
  4105.5 2053.29  4225.7 2045.19  4404.6 2024.13  4530.4  2012.7  4566.7 2006.08
  4583.5 1998.98  4597.5 1996.96  4777.3 1998.54  4790.3 1996.13  4829.5 1995.74
  4857.4 1998.31  4879.8 1995.79  4910.5 1986.78  4987.1 1983.78  4988.1 1983.28
  5039.9 1983.78  5043.1 1997.88  5049.2 2001.58  5057.9    2003    5064 2010.56
  5072.8 2012.83  5080.2 2017.35  5099.8 2024.41  5150.4 2031.65  5221.9 2039.04
  5316.9 2045.72  5373.6 2052.28  5501.7 2074.66  5573.7 2092.64  5610.3 2098.21
#Mann= 5 ,-1 , 0
  4105.5      .1       0  4777.3    .035       0  4987.1    .035       0
  5039.9    .035       0  5080.2      .1       0
Bank Sta=4987.1,5039.9
XS Rating Curve= 0 ,0
Exp/Cntr=0.3,0.1

Type RM Length L Ch R = 1 ,82010   ,573,573,573
BEGIN DESCRIPTION:
South Fork Guadalupe River 119.0
END DESCRIPTION:
XS GIS Cut Line= 3
        1826675.       13899625.        1827325.       13898875.
        1827425.     13898474.99
#Sta/Elev= 30
  4007.2 2047.27    4113 2039.57  4247.9 2026.64  4354.3  2020.8  4397.1 2016.45
  4450.3 2016.19  4503.4 2014.34  4574.7 2006.13  4630.7 2002.28  4638.3 1996.86
  4644.9 1996.64  4653.5 1991.81  4722.8  1992.1  4787.4 1996.93  4886.2 1998.22
  4964.1 1990.91    4970 1983.79    4971 1983.29  5022.8 1983.79  5071.8 1985.05
  5082.1 1990.61  5092.4 2000.18  5113.1 2028.01  5141.4 2038.36  5174.9 2045.47
  5182.6 2049.43  5216.1 2053.62  5352.7 2080.14  5388.8 2090.08    5412 2093.41
#Mann= 6 ,-1 , 0
  4007.2      .1       0    4113    .035       0  4450.3     .07       0
  4653.5      .1       0    4970     .05       0  5022.8      .1       0
Bank Sta=4970,5022.8
XS Rating Curve= 0 ,0
Exp/Cntr=0.3,0.1

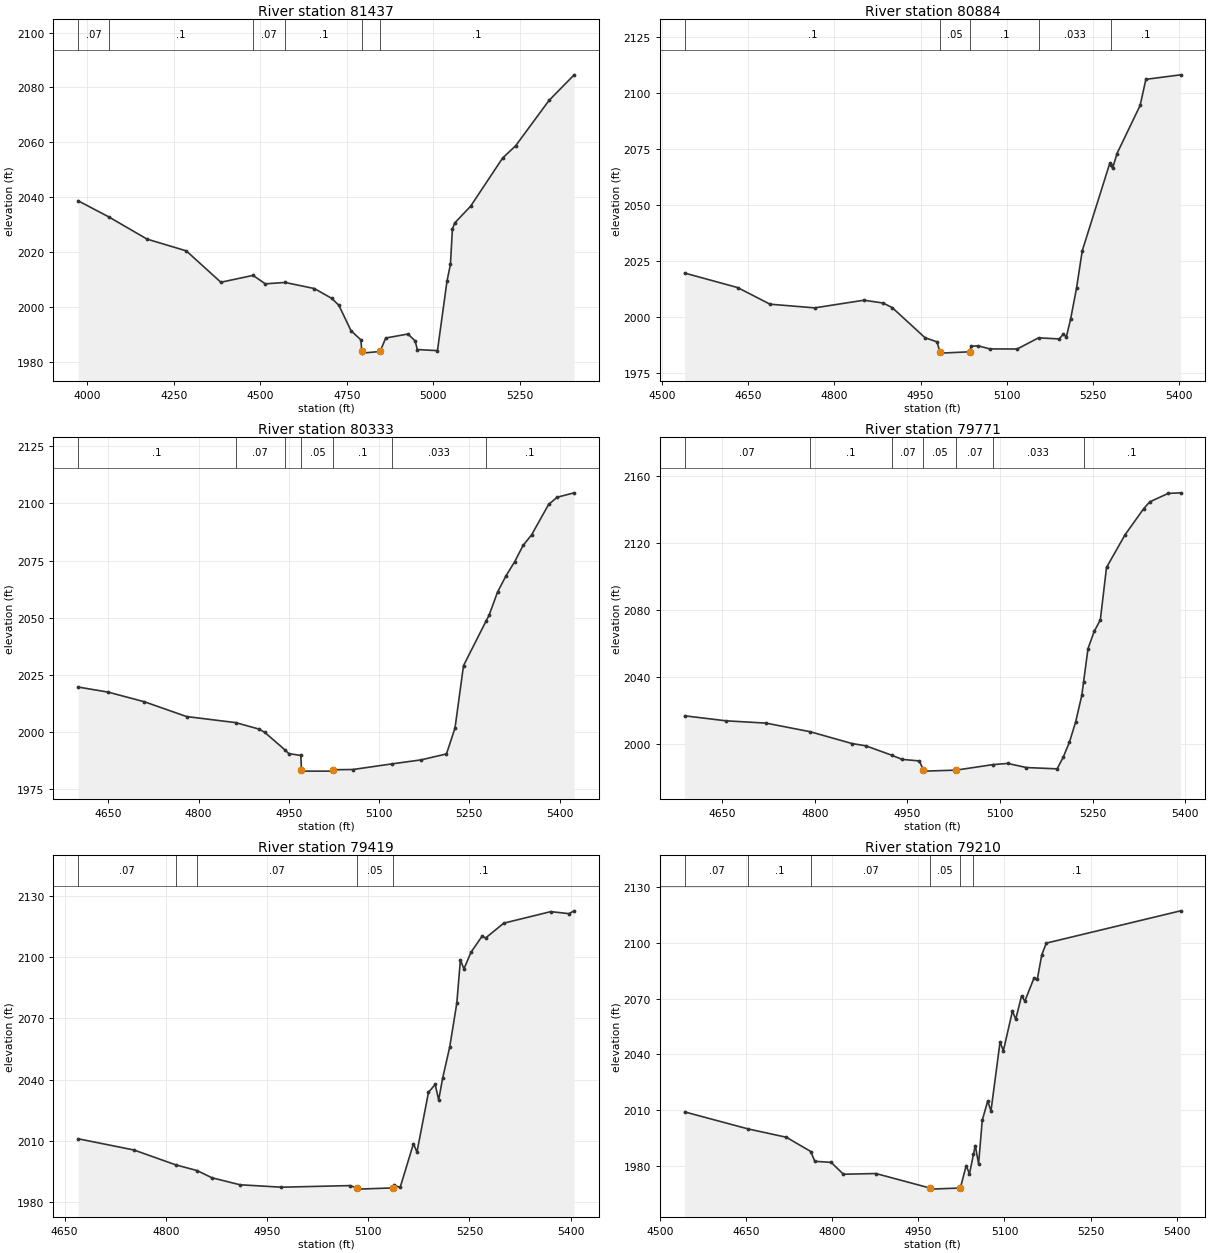
Type RM Length L Ch R = 1 ,81437   ,553,553,553
BEGIN DESCRIPTION:
South Fork Guadalupe River 118.0
END DESCRIPTION:
XS GIS Cut Line= 3
      1827174.97     13899875.03        1827825.       13899075.
      1828174.97     13898875.02
#Sta/Elev= 30
  3973.6 2038.63  4061.7  2032.8  4172.6 2024.68  4286.1 2020.39    4386 2008.95
  4479.1 2011.45  4514.6 2008.37  4571.4 2008.88  4656.5 2006.65  4706.3  2003.1
  4727.2 2000.56  4762.3  1991.3  4791.1 1987.91  4793.4 1983.71  4794.4 1983.11
  4846.3 1983.71  4862.7 1988.62  4926.9 1990.08  4947.7 1987.58  4954.1 1984.41
  5012.3 1984.02  5039.7 2009.24  5049.8 2015.47  5055.5 2028.29    5062 2030.55
  5108.1 2036.66  5200.9 2054.27  5238.4 2058.71  5334.8 2075.23  5407.5 2084.57
#Mann= 6 ,-1 , 0
  3973.6     .07       0  4061.7      .1       0  4479.1     .07       0
  4571.4      .1       0  4793.4     .05       0  4846.3      .1       0
Bank Sta=4793.4,4846.3
XS Rating Curve= 0 ,0
Exp/Cntr=0.3,0.1

Type RM Length L Ch R = 1 ,80884   ,551,551,551
BEGIN DESCRIPTION:
South Fork Guadalupe River 117.0
END DESCRIPTION:
XS GIS Cut Line= 3
      1827575.02     13899824.98        1827925.       13899525.
      1828325.03       13899575.
#Sta/Elev= 30
    4539 2019.67  4631.2 2013.21  4687.7 2005.78  4765.6 2004.14  4851.2 2007.56
  4884.7 2006.31  4900.6 2004.26  4957.7 1990.83  4978.6 1988.97  4983.6 1984.54
  4984.6 1983.94  5036.5 1984.54  5037.7 1987.01  5050.3 1987.21  5070.5 1985.83
  5118.4 1985.78  5155.5 1990.77  5191.4 1990.28    5199 1992.44    5204 1991.15
  5211.6 1999.35  5221.7 2012.89  5231.7 2029.61  5279.6 2068.63    5281 2068.05
  5284.7 2066.53  5292.2 2072.99  5332.5 2094.47  5342.6 2106.14  5403.1 2108.15
#Mann= 5 ,-1 , 0
    4539      .1       0  4983.6     .05       0  5036.5      .1       0
  5155.5    .033       0    5281      .1       0
Bank Sta=4983.6,5036.5
XS Rating Curve= 0 ,0
Exp/Cntr=0.3,0.1

Type RM Length L Ch R = 1 ,80333   ,562,562,562
BEGIN DESCRIPTION:
South Fork Guadalupe River 116.0
END DESCRIPTION:
XS GIS Cut Line= 3
        1827675.       13900025.        1828075.       13900025.
      1828375.03     13899724.97
#Sta/Elev= 30
    4600 2019.73    4650  2017.5    4710  2013.3    4780 2006.85  4861.8 2004.18
    4900  2001.4    4910 1999.94  4943.2 1992.38    4950 1990.67    4970 1989.82
  4971.1 1983.59  4972.1 1982.99  5022.9 1982.99    5024 1983.59  5056.6  1983.7
  5121.3 1986.15  5169.7  1987.9  5212.1 1990.51  5226.3 2001.86  5240.4 2029.09
  5277.9 2048.57  5282.8 2051.04    5297 2061.26  5311.1 2068.38  5325.3 2074.41
  5339.4 2081.61  5353.6 2086.26  5381.8  2099.5    5396 2102.67  5424.3  2104.6
#Mann= 7 ,-1 , 0
    4600      .1       0  4861.8     .07       0  4943.2      .1       0
  4971.1     .05       0    5024      .1       0  5121.3    .033       0
  5277.9      .1       0
Bank Sta=4971.1,5024
XS Rating Curve= 0 ,0
Exp/Cntr=0.3,0.1

Type RM Length L Ch R = 1 ,79771   ,352,352,352
BEGIN DESCRIPTION:
South Fork Guadalupe River 115.0
END DESCRIPTION:
XS GIS Cut Line= 3
        1827725.       13900325.        1828075.       13900525.
      1828474.99       13900525.
#Sta/Elev= 30
  4589.3    2017  4656.2 2014.01    4721 2012.64  4792.1 2007.54  4860.7 2000.42
  4882.3 1999.13  4924.3 1993.54  4941.3 1991.02  4969.4 1990.07  4975.9  1984.6
    4977    1984  5028.9  1984.6  5088.5 1987.89  5112.4  1988.6  5142.4 1986.15
  5192.4 1985.36  5202.4 1992.38  5212.4 2001.36  5222.4 2013.29  5232.4 2029.24
  5235.2 2037.03  5242.4 2057.05  5252.4 2067.29  5262.4 2074.26  5272.4 2105.49
  5302.4 2124.96  5332.4 2140.47  5342.4 2144.62  5372.4 2149.67  5392.4    2150
#Mann= 7 ,-1 , 0
  4589.3     .07       0  4792.1      .1       0  4924.3     .07       0
  4975.9     .05       0  5028.9     .07       0  5088.5    .033       0
  5235.2      .1       0
Bank Sta=4975.9,5028.9
XS Rating Curve= 0 ,0
Exp/Cntr=0.3,0.1

Type RM Length L Ch R = 1 ,79419   ,209,209,209
BEGIN DESCRIPTION:
South Fork Guadalupe Rier 114.1
END DESCRIPTION:
XS GIS Cut Line= 4
      1827751.54     13900652.58      1827963.38     13900805.38
      1828156.09     13900880.04      1828410.63     13900798.65
#Sta/Elev= 30
  4670.1 2010.92  4752.8 2005.42  4814.9 1998.11  4846.3 1995.34  4868.2 1991.81
  4909.9 1988.37  4971.2 1987.18  5072.5 1987.96  5083.6 1986.83  5084.7 1986.23
  5136.6 1986.83  5137.9 1988.15  5147.3 1987.06    5167 2008.51  5172.2 2004.41
  5189.3 2033.73  5199.2 2037.58  5204.4 2029.98  5210.3 2040.73  5220.8 2055.99
  5231.3 2077.56  5236.6  2098.7  5241.8 2094.24  5252.3 2102.42  5268.7 2110.29
    5274 2109.44  5300.9  2116.7  5370.5 2122.36  5397.4 2121.37  5405.2 2122.75
#Mann= 5 ,-1 , 0
  4670.1     .07       0  4814.9      .1       0  4846.3     .07       0
  5083.6     .05       0  5136.6      .1       0
Bank Sta=5083.6,5136.6
XS Rating Curve= 0 ,0
Exp/Cntr=0.3,0.1

Type RM Length L Ch R = 1 ,79210   ,585,585,585
BEGIN DESCRIPTION:
South Fork Guadalupe River 114.0
END DESCRIPTION:
XS GIS Cut Line= 3
      1827725.02     13900725.02        1828075.       13901025.
      1828425.03     13900824.98
#Sta/Elev= 30
  4542.8 2008.94  4653.6 1999.74    4720 1995.27  4762.6 1987.57  4769.4 1982.32
    4798 1981.73  4819.4 1975.34  4875.9 1975.72  4970.1 1967.91  4971.2 1967.31
  5023.1 1967.91  5033.3 1979.96    5039 1975.56    5046 1986.12  5049.1  1990.8
  5054.9 1980.94  5061.3 2004.42  5070.7 2014.73  5076.5  2009.5  5092.3 2046.65
  5098.1 2041.92  5113.9 2063.35  5119.6 2058.88  5129.7  2071.4  5135.5 2068.69
  5151.3 2080.97  5157.1 2080.32    5165 2093.64  5172.9 2099.92  5406.9 2117.33
#Mann= 6 ,-1 , 0
  4542.8     .07       0  4653.6      .1       0  4762.6     .07       0
  4970.1     .05       0  5023.1     .07       0    5046      .1       0
Bank Sta=4970.1,5023.1
XS Rating Curve= 0 ,0
Exp/Cntr=0.3,0.1

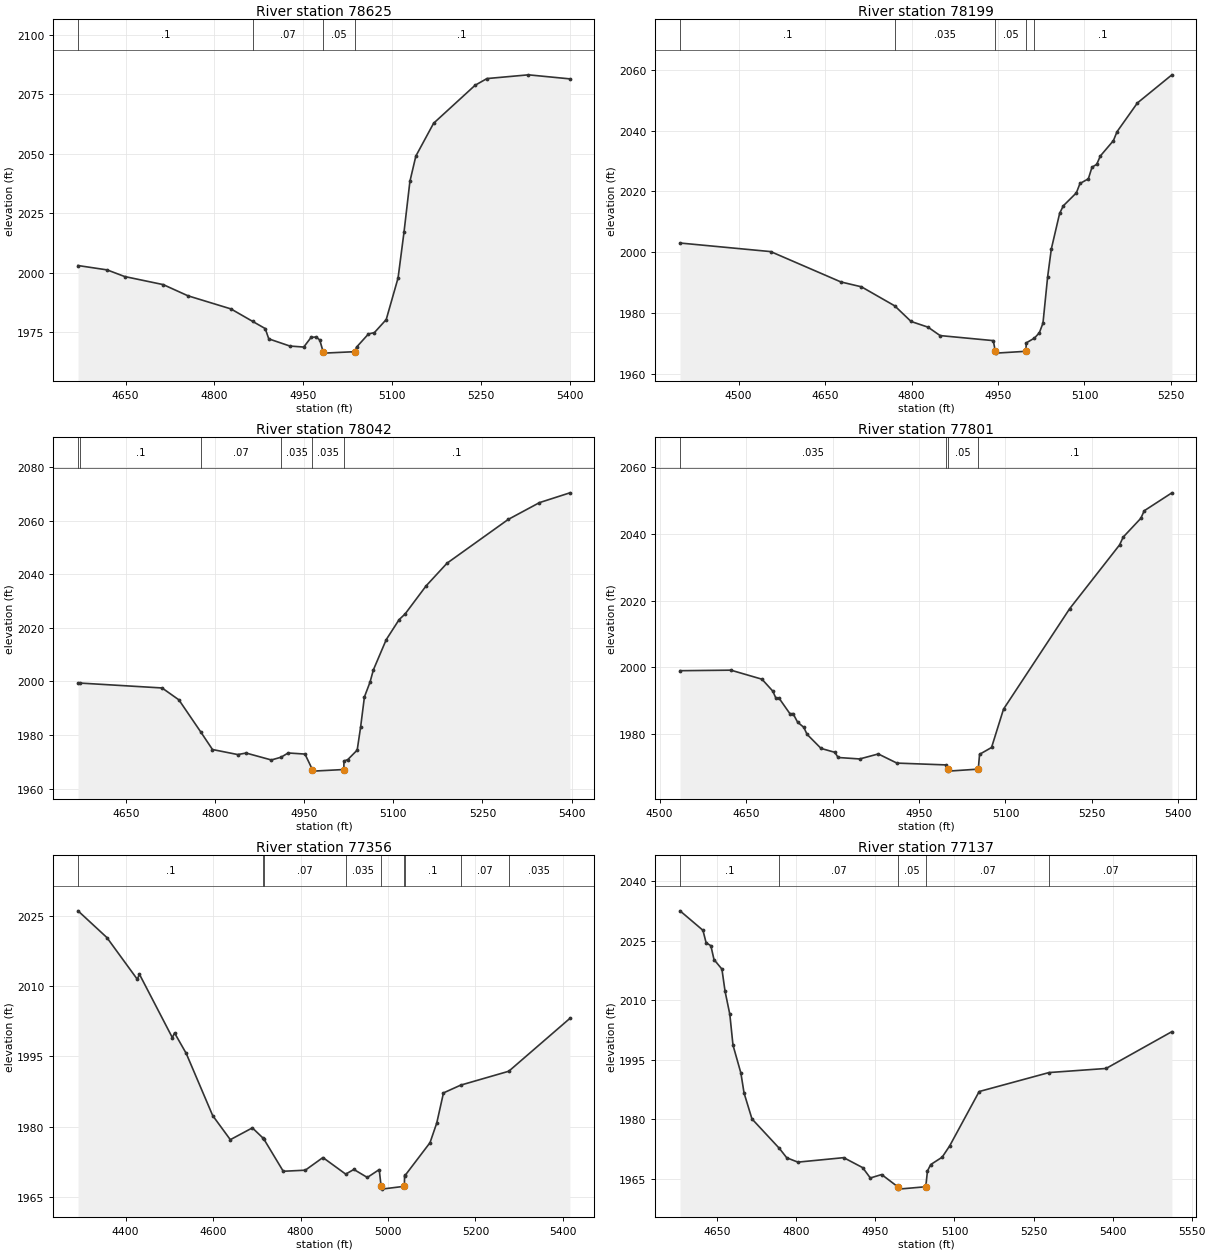
Type RM Length L Ch R = 1 ,78625   ,426,426,426
BEGIN DESCRIPTION:
South Fork Guadalupe River 113.0
END DESCRIPTION:
XS GIS Cut Line= 3
      1827474.98     13901124.97        1827725.       13901475.
      1828125.05       13901475.
#Sta/Elev= 30
  4569.8 2003.09    4619 2001.26  4648.5 1998.48  4713.6 1995.09  4755.4 1990.39
  4827.9 1984.89  4864.8 1979.62  4885.7 1976.65  4891.8 1972.32  4927.4 1969.31
  4950.8 1968.89  4963.1 1972.92  4971.7 1973.13  4977.8 1971.85  4983.5 1966.94
  4984.5 1966.34  5036.5 1966.94    5040 1968.88    5060 1974.38    5070 1974.94
    5090 1980.43    5110 1997.88    5120 2017.07    5130 2038.43    5140 2049.02
    5170  2062.8    5240 2078.73    5260 2081.54    5330 2083.11    5400 2081.41
#Mann= 4 ,-1 , 0
  4569.8      .1       0  4864.8     .07       0  4983.5     .05       0
  5036.5      .1       0
Bank Sta=4983.5,5036.5
XS Rating Curve= 0 ,0
Exp/Cntr=0.3,0.1

Type RM Length L Ch R = 1 ,78199   ,157,157,157
BEGIN DESCRIPTION:
South Fork Guadalupe River 112.1
END DESCRIPTION:
XS GIS Cut Line= 3
       1827097.8      13901313.2      1827421.39     13901767.41
      1827654.48      13901948.9
#Sta/Elev= 30
  4398.5    2003  4555.8 2000.17  4677.5 1990.18  4713.2 1988.57  4770.9  1982.3
  4799.2 1977.16  4828.7 1975.28  4849.6 1972.51  4941.8 1970.85  4945.4 1967.33
  4946.4 1966.73  4998.4 1967.33    4999  1970.1  5013.2 1971.68  5021.7 1973.43
    5028 1976.61  5036.1 1991.88  5042.5 2001.05  5056.9 2012.77  5063.3 2015.26
  5085.9 2019.52  5092.2 2022.61  5106.7 2024.14    5113 2027.96  5121.2 2028.92
  5127.5 2031.67  5150.1 2036.71  5156.5 2039.68  5191.8 2049.14  5251.6  2058.4
#Mann= 5 ,-1 , 0
  4398.5      .1       0  4770.9    .035       0  4945.4     .05       0
  4998.4    .035       0  5013.2      .1       0
Bank Sta=4945.4,4998.4
XS Rating Curve= 0 ,0
Exp/Cntr=0.3,0.1

Type RM Length L Ch R = 1 ,78042   ,241,241,241
BEGIN DESCRIPTION:
South Fork Guadalupe River 112.0
END DESCRIPTION:
XS GIS Cut Line= 3
      1827025.02     13901575.02        1827325.       13901875.
      1827675.04     13902075.02
#Sta/Elev= 30
  4569.7 1999.39  4573.1 1999.39  4711.1 1997.56  4739.4 1993.12  4776.2 1981.12
  4795.9 1974.57  4838.4 1972.69  4852.5 1973.25  4894.9 1970.67  4911.2 1971.69
  4923.2 1973.28  4951.5 1972.87  4963.9  1967.1    4965  1966.5  5016.9  1967.1
    5017 1970.25  5023.5 1970.81  5039.3 1974.35    5045 1982.85  5051.5 1994.23
  5060.9 1999.74  5066.6 2004.35  5088.2 2015.62  5109.8 2023.07  5119.9  2025.2
  5155.2 2035.68  5190.5 2044.17  5293.4 2060.51  5345.9 2066.78  5397.1 2070.44
#Mann= 6 ,-1 , 0
  4569.7    .035       0  4573.1      .1       0  4776.2     .07       0
  4911.2    .035       0  4963.9    .035       0  5016.9      .1       0
Bank Sta=4963.9,5016.9
XS Rating Curve= 0 ,0
Exp/Cntr=0.3,0.1

Type RM Length L Ch R = 1 ,77801   ,445,445,445
BEGIN DESCRIPTION:
Mapping XS eddca48b
END DESCRIPTION:
XS GIS Cut Line= 4
      1826928.32     13901565.46      1827080.64     13901947.68
      1827289.53     13902120.41      1827450.28     13902178.39
#Sta/Elev= 30
  4535.4    1999  4623.7 1999.16  4677.6 1996.45  4696.4 1992.87  4701.9  1990.7
  4707.3 1990.74  4726.2 1986.08  4731.5 1986.14  4739.4 1983.57  4750.2 1982.01
  4755.8 1979.92  4780.1 1975.69    4804 1974.52  4809.7 1972.97  4847.1 1972.53
  4879.4 1974.03  4911.7 1971.29  4997.4 1970.74  4999.9 1969.48    5001 1968.88
  5052.9 1969.48  5055.1 1973.92  5075.9 1975.97  5096.7 1987.48  5211.4 2017.59
  5298.1 2036.75  5304.3 2039.07    5335 2044.73  5340.7 2046.96  5388.8 2052.35
#Mann= 4 ,-1 , 0
  4535.4    .035       0  4997.4     .07       0  4999.9     .05       0
  5052.9      .1       0
Bank Sta=4999.9,5052.9
XS Rating Curve= 0 ,0
Exp/Cntr=0.3,0.1

Type RM Length L Ch R = 1 ,77356   ,219,219,219
BEGIN DESCRIPTION:
Mapping XS 7e857274
END DESCRIPTION:
XS GIS Cut Line= 3
      1826622.54     13901439.52      1826695.39     13902016.33
      1826979.08     13902479.45
#Sta/Elev= 30
  4291.3 2026.03  4357.3 2020.33  4426.7 2011.44  4431.8 2012.49    4507 1998.97
    4512 1999.98  4538.7  1995.6  4599.2 1982.34  4639.5  1977.2  4689.9 1979.72
  4715.2 1977.46    4716 1977.36  4760.5 1970.46  4810.9 1970.69  4851.2 1973.39
  4903.3 1969.85  4921.9 1970.85  4952.7 1969.14  4979.9 1970.82  4984.2 1967.25
  4985.3 1966.65  5037.3 1967.25  5037.9 1969.42  5039.7 1969.65    5096 1976.56
  5111.4 1980.75  5126.8 1987.18  5166.2 1988.84    5276  1991.8  5415.8 2003.08
#Mann= 9 ,-1 , 0
  4291.3      .1       0  4715.2    .035       0    4716     .07       0
  4903.3    .035       0  4984.2    .035       0  5037.3    .035       0
  5039.7      .1       0  5166.2     .07       0    5276    .035       0
Bank Sta=4984.2,5037.3
XS Rating Curve= 0 ,0
Exp/Cntr=0.3,0.1

Type RM Length L Ch R = 1 ,77137   ,218,218,218
BEGIN DESCRIPTION:
South Fork Guadalupe River 111.0
END DESCRIPTION:
XS GIS Cut Line= 3
      1826325.02     13901825.03      1826596.75     13902230.37
        1826929.     13902526.87
#Sta/Elev= 30
  4579.2 2032.54  4622.7 2027.63  4628.7 2024.49  4637.7 2023.74  4643.7 2020.24
  4658.7 2017.84  4664.7 2012.22  4673.7 2006.43  4679.7 1998.67  4694.7 1991.61
  4700.7 1986.59  4715.7 1980.05  4767.9 1972.58  4781.7 1970.24  4802.8 1969.14
  4889.8 1970.27  4925.8 1967.75  4940.3 1965.14  4961.8 1966.01  4992.3 1962.93
  4993.4 1962.33  5045.5 1962.93  5048.7 1966.92  5054.9 1968.53  5076.6 1970.39
  5090.8 1973.23  5146.8 1986.95  5279.4 1991.74  5387.6 1992.77  5512.5 2002.06
#Mann= 5 ,-1 , 0
  4579.2      .1       0  4767.9     .07       0  4992.3     .05       0
  5045.5     .07       0  5279.4     .07       0
Bank Sta=4992.3,5045.5
XS Rating Curve= 0 ,0
Exp/Cntr=0.3,0.1

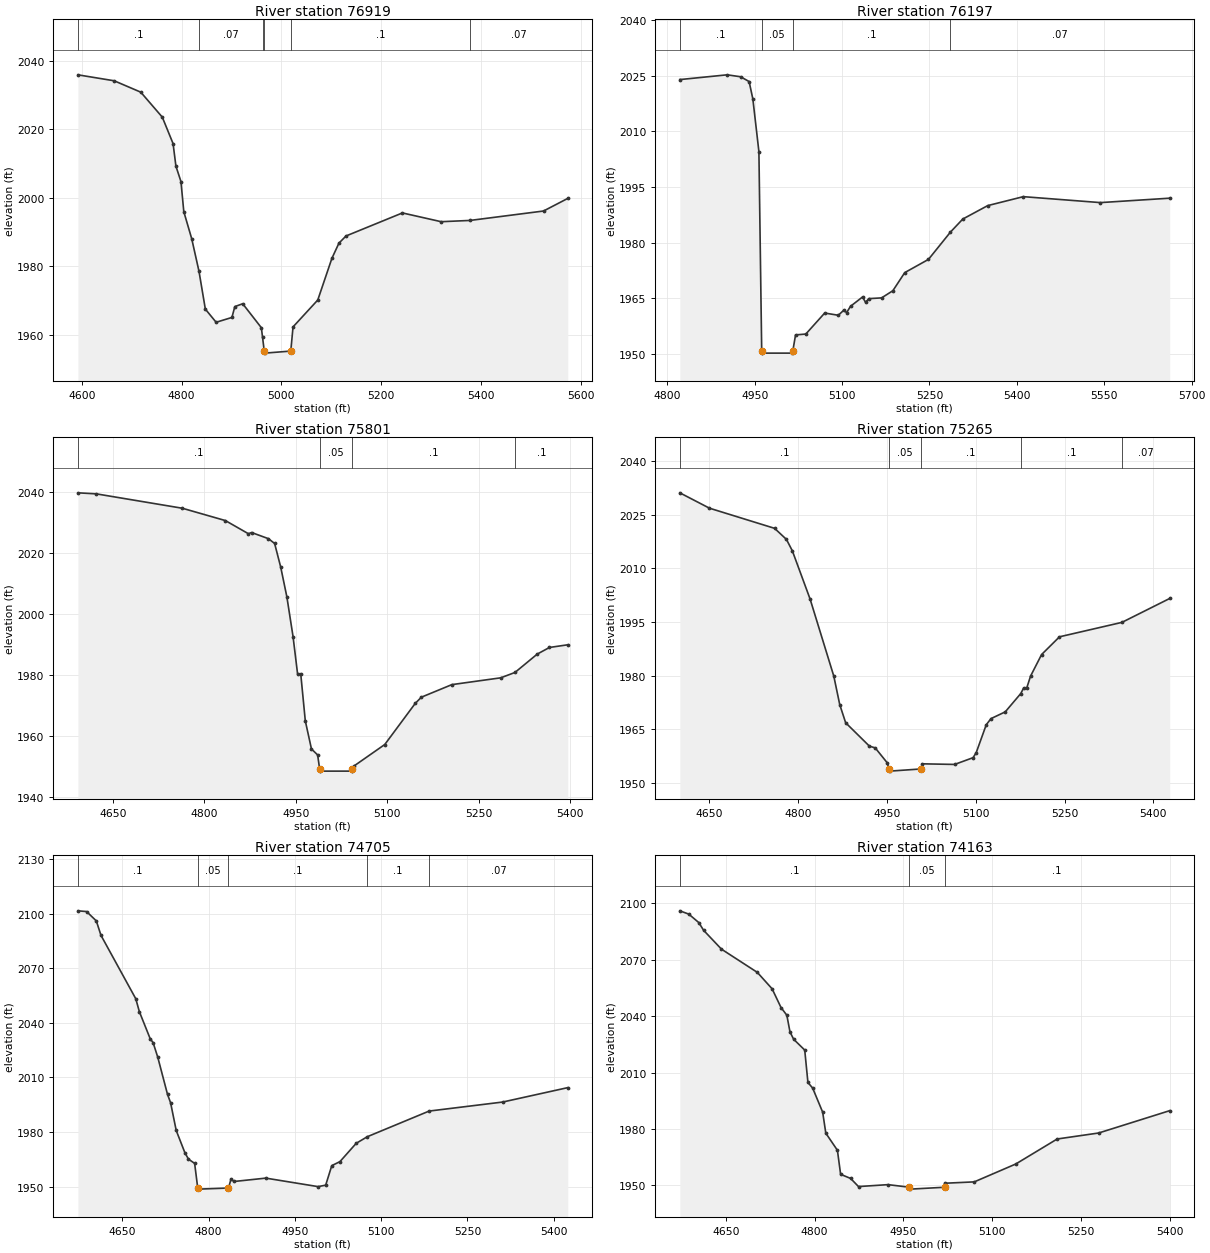
Type RM Length L Ch R = 1 ,76919   ,722,722,722
BEGIN DESCRIPTION:
South Fork Guadalupe River 110.0
END DESCRIPTION:
XS GIS Cut Line= 3
        1826175.     13901925.01        1826375.       13902275.
      1826781.28     13902687.52
#Sta/Elev= 30
  4592.1 2035.88  4664.8 2034.14  4718.1 2030.82  4761.3 2023.52  4782.9 2015.79
  4788.6 2009.21  4798.7 2004.72  4804.4 1995.92  4820.3    1988  4834.9 1978.48
  4847.6 1967.46  4869.2 1963.62  4900.9 1965.03  4906.7  1968.2  4922.5 1969.03
  4959.9 1962.03  4962.2 1959.33  4965.7 1955.21  4966.8 1954.61  5018.9 1955.21
  5023.4 1962.27    5073 1970.12  5101.3 1982.28  5115.4 1986.72  5129.6 1988.82
  5242.7 1995.55  5320.4 1992.99  5378.4 1993.36  5525.6 1996.11  5574.2 1999.79
#Mann= 6 ,-1 , 0
  4592.1      .1       0  4834.9     .07       0  4962.2      .1       0
  4965.7     .05       0  5018.9      .1       0  5378.4     .07       0
Bank Sta=4965.7,5018.9
XS Rating Curve= 0 ,0
Exp/Cntr=0.3,0.1

Type RM Length L Ch R = 1 ,76197   ,396,396,396
BEGIN DESCRIPTION:
South Fork Guadalupe River 109.1
END DESCRIPTION:
XS GIS Cut Line= 3
      1825755.47     13902815.21      1826081.95     13902712.88
      1826571.88     13902805.21
#Sta/Elev= 30
  4821.6 2023.97  4902.8 2025.25  4925.9 2024.73  4940.5 2023.44  4946.9 2018.75
  4957.3 2004.56  4962.1 1950.88  4963.2 1950.28  5014.4 1950.28  5015.5 1950.88
  5020.2 1955.19  5037.8 1955.42  5070.2 1961.08  5093.6 1960.48  5102.7 1961.81
  5107.9 1961.21  5114.5 1962.89  5135.1  1965.4  5140.3 1963.98    5146 1964.96
  5167.8 1965.16  5187.2 1967.09  5207.6 1971.97  5248.3 1975.53  5286.1  1982.9
  5307.2  1986.4    5350 1990.02  5411.1 1992.43  5543.4 1990.83  5662.3 1992.02
#Mann= 4 ,-1 , 0
  4821.6      .1       0  4962.1     .05       0  5015.5      .1       0
  5286.1     .07       0
Bank Sta=4962.1,5015.5
XS Rating Curve= 0 ,0
Exp/Cntr=0.3,0.1

Type RM Length L Ch R = 1 ,75801   ,536,536,536
BEGIN DESCRIPTION:
South Fork Guadalupe River 109.0
END DESCRIPTION:
XS GIS Cut Line= 3
      1825525.03       13903175.        1825925.       13903125.
      1826325.02       13903125.
#Sta/Elev= 30
  4592.7 2039.89  4622.9 2039.55    4764 2034.82  4834.5 2030.77  4872.3 2026.44
  4877.4 2026.85  4905.1 2024.82  4915.2 2023.25  4925.2 2015.47  4935.3 2005.68
  4945.4 1992.67  4952.9 1980.28    4958 1980.45  4965.5 1964.95  4975.6 1955.71
  4985.7 1953.76  4989.1 1949.03  4990.2 1948.43  5041.4 1948.43  5042.5 1949.03
  5045.8 1950.18  5095.8 1957.18  5145.8  1970.7  5155.8 1972.73  5205.8 1976.86
  5285.8 1979.09  5309.2 1980.85  5345.8  1986.9  5365.8 1989.07  5395.8 1989.95
#Mann= 4 ,-1 , 0
  4592.7      .1       0  4989.1     .05       0  5042.5      .1       0
  5309.2      .1       0
Bank Sta=4989.1,5042.5
XS Rating Curve= 0 ,0
Exp/Cntr=0.3,0.1

Type RM Length L Ch R = 1 ,75265   ,560,560,560
BEGIN DESCRIPTION:
South Fork Guadalupe River 108.0
END DESCRIPTION:
XS GIS Cut Line= 3
      1825775.04       13903575.        1826175.       13903575.
      1826575.04     13903424.98
#Sta/Elev= 30
  4600.4 2031.06  4650.4 2026.77  4760.4 2021.14  4780.4 2018.05  4790.4 2014.85
  4820.4 2001.36  4860.4 1979.84  4870.4  1971.9  4880.4 1966.82  4920.4  1960.3
  4930.4 1959.78  4950.4 1955.67  4953.7  1953.9  4954.8  1953.3  5007.1  1953.9
  5010.1 1955.34  5064.4 1955.17  5095.6 1957.06  5100.9 1958.47  5117.8 1966.25
  5125.8 1967.97  5149.9 1969.86  5176.2 1974.99    5181 1976.54  5186.4 1976.63
  5192.6 1979.83  5211.3 1985.88  5241.5 1990.83  5346.9 1994.86  5427.6 2001.54
#Mann= 5 ,-1 , 0
  4600.4      .1       0  4953.7     .05       0  5007.1      .1       0
  5176.2      .1       0  5346.9     .07       0
Bank Sta=4953.7,5007.1
XS Rating Curve= 0 ,0
Exp/Cntr=0.3,0.1

Type RM Length L Ch R = 1 ,74705   ,542,542,542
BEGIN DESCRIPTION:
South Fork Guadalupe River 107.0
END DESCRIPTION:
XS GIS Cut Line= 3
        1826375.       13904375.        1826525.       13903975.
      1826825.02     13903674.98
#Sta/Elev= 30
  4572.8 2101.57  4587.9 2101.17  4604.8 2096.03  4612.9 2088.09  4673.4 2053.23
  4679.6 2046.16  4698.3 2031.37  4703.6 2029.03  4711.6 2021.11  4728.6 2000.62
  4733.9 1996.07  4743.7 1980.81  4758.8 1968.56    4765 1965.06  4775.7 1962.74
  4781.1 1949.18  4782.1 1948.58  4834.5 1949.18  4838.9 1954.05  4844.3 1952.78
  4899.4 1954.63  4990.2 1949.96  5003.5 1950.76  5014.1  1961.5  5028.3  1963.7
  5056.6 1973.78  5075.9  1977.4  5183.3 1991.49  5311.1 1996.45  5424.3 2004.37
#Mann= 5 ,-1 , 0
  4572.8      .1       0  4781.1     .05       0  4834.5      .1       0
  5075.9      .1       0  5183.3     .07       0
Bank Sta=4781.1,4834.5
XS Rating Curve= 0 ,0
Exp/Cntr=0.3,0.1

Type RM Length L Ch R = 1 ,74163   ,559,559,559
BEGIN DESCRIPTION:
South Fork Guadalupe River 106.0
END DESCRIPTION:
XS GIS Cut Line= 3
        1826475.       13904475.        1826875.       13904325.
        1826875.       13903925.
#Sta/Elev= 30
  4572.5 2096.08  4587.6 2094.33  4604.5 2089.83  4612.6 2085.73  4642.8 2075.68
  4703.3 2063.33  4728.3 2054.58  4743.4 2044.59  4753.2 2040.51  4758.5 2031.64
  4764.7 2027.72  4783.4 2021.97  4788.8 2004.72  4796.8 2001.73  4813.7 1988.91
    4819 1977.74  4838.6 1968.63    4844 1955.85  4860.9 1953.65  4874.2 1949.32
  4924.1 1950.35  4960.3 1948.96  4961.7 1947.96  5019.6 1948.96  5019.7 1951.09
  5069.7 1951.82  5139.7 1961.32  5209.7 1974.64  5279.7 1977.83  5399.7 1989.72
#Mann= 3 ,-1 , 0
  4572.5      .1       0  4960.3     .05       0  5019.6      .1       0
Bank Sta=4960.3,5019.6
XS Rating Curve= 0 ,0
Exp/Cntr=0.3,0.1

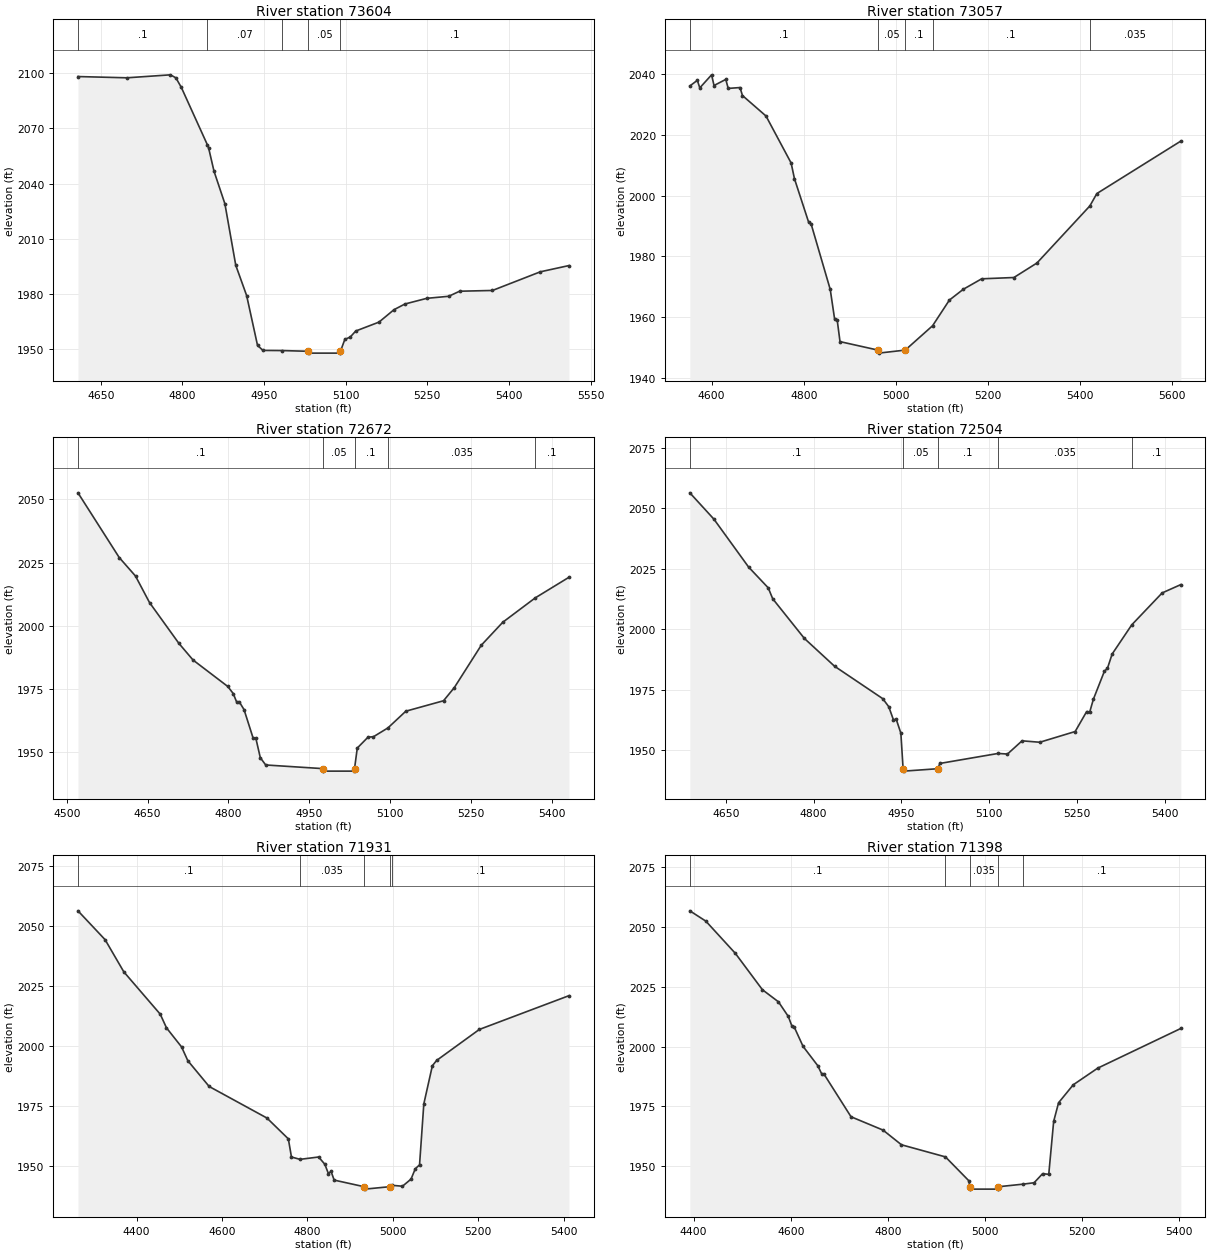
Type RM Length L Ch R = 1 ,73604   ,547,547,547
BEGIN DESCRIPTION:
South Fork Guadalupe River 105.0
END DESCRIPTION:
XS GIS Cut Line= 3
        1827375.     13904724.95        1827375.       13904325.
        1827325.     13903825.04
#Sta/Elev= 30
  4607.9 2098.28  4697.9  2097.6  4777.9 2099.22  4787.9 2097.56  4797.9 2092.34
  4845.8 2061.07  4847.9 2059.53  4857.9 2046.75  4877.9 2029.03  4897.9 1995.51
  4917.9    1979  4937.9 1951.89  4947.9 1949.15  4982.6 1949.08    5031 1948.68
  5032.4 1947.68  5088.8 1947.68  5090.3 1948.68  5098.3 1955.13  5108.3 1956.45
  5118.4 1959.72  5161.1 1964.57  5188.7 1971.34  5208.8 1974.43    5249 1977.52
  5289.2 1978.63  5309.3 1981.39  5369.6  1981.8  5457.6 1991.96  5510.3 1995.37
#Mann= 5 ,-1 , 0
  4607.9      .1       0  4845.8     .07       0  4982.6      .1       0
    5031     .05       0  5090.3      .1       0
Bank Sta=5031,5090.3
XS Rating Curve= 0 ,0
Exp/Cntr=0.3,0.1

Type RM Length L Ch R = 1 ,73057   ,385,385,385
BEGIN DESCRIPTION:
South Fork Guadalupe River 104.0
END DESCRIPTION:
XS GIS Cut Line= 3
      1827673.42     13904652.16        1827825.       13904225.
      1827826.19     13903612.66
#Sta/Elev= 30
  4552.7 2036.13    4569 2037.99  4574.3  2035.5  4599.9  2039.8  4605.2 2036.28
  4630.7 2038.29    4636 2035.32  4661.6 2035.61  4666.9 2032.98    4718 2026.23
  4772.5 2010.76  4779.8 2005.55  4810.6 1991.21  4815.9 1990.67  4857.4  1969.1
    4867 1959.23  4872.4 1959.14  4878.6 1951.91  4960.9 1949.12  4962.3 1948.12
  5020.2 1949.12  5079.5 1957.14    5116  1965.6    5146 1969.14    5186  1972.6
    5256 1973.03    5306 1977.81  5420.9 1996.63    5436 2000.69  5618.3 2017.98
#Mann= 5 ,-1 , 0
  4552.7      .1       0  4960.9     .05       0  5020.2      .1       0
  5079.5      .1       0  5420.9    .035       0
Bank Sta=4960.9,5020.2
XS Rating Curve= 0 ,0
Exp/Cntr=0.3,0.1

Type RM Length L Ch R = 1 ,72672   ,168,168,168
BEGIN DESCRIPTION:
South Fork Guadalupe River 103.1
END DESCRIPTION:
XS GIS Cut Line= 3
      1828153.48     13904650.98      1828193.85     13904326.76
      1828179.53     13903742.15
#Sta/Elev= 30
  4520.8 2052.62  4597.4 2026.97  4627.6 2019.64  4653.6 2009.14  4708.2 1992.94
  4734.4 1986.36  4798.9 1975.87    4809 1973.07  4815.2 1969.79  4820.2  1969.8
  4829.1 1966.69  4845.9 1955.44  4850.9 1955.44  4859.3 1947.63  4869.3 1944.76
  4974.8 1943.32  4976.3 1942.32  5032.7 1942.32  5034.2 1943.32  5039.3 1951.47
  5059.3  1955.8  5069.3 1955.95  5096.2 1959.45  5129.4 1966.07  5199.4 1970.21
  5219.4 1975.42  5269.4  1992.2  5309.4 2001.33  5369.7 2010.99  5432.3 2019.16
#Mann= 5 ,-1 , 0
  4520.8      .1       0  4974.8     .05       0  5034.2      .1       0
  5096.2    .035       0  5369.7      .1       0
Bank Sta=4974.8,5034.2
XS Rating Curve= 0 ,0
Exp/Cntr=0.3,0.1

Type RM Length L Ch R = 1 ,72504   ,573,573,573
BEGIN DESCRIPTION:
South Fork Guadalupe River 103.0
END DESCRIPTION:
XS GIS Cut Line= 3
        1828175.     13904674.99        1828275.       13904275.
        1828425.       13903875.
#Sta/Elev= 30
  4588.3 2056.48  4629.5 2045.57  4688.8 2025.73  4722.3 2017.14    4730 2012.61
  4784.1  1996.2  4835.7 1984.68  4918.1 1971.25  4928.4 1967.92  4936.2  1962.6
  4941.3 1962.62  4949.1 1956.95  4952.9 1942.24  4954.3 1941.24  5012.3 1942.24
  5015.7 1944.42  5115.3 1948.56  5131.4 1948.32  5156.3 1953.79  5186.6  1953.2
  5247.1 1957.64  5266.7 1965.89    5272 1965.74  5278.3 1971.05    5297 1982.56
  5302.3 1983.82  5310.3 1989.72  5343.9 2001.83  5395.8 2015.03  5427.8 2018.49
#Mann= 5 ,-1 , 0
  4588.3      .1       0  4952.9     .05       0  5012.3      .1       0
  5115.3    .035       0  5343.9      .1       0
Bank Sta=4952.9,5012.3
XS Rating Curve= 0 ,0
Exp/Cntr=0.3,0.1

Type RM Length L Ch R = 1 ,71931   ,533,533,533
BEGIN DESCRIPTION:
South Fork Guadalupe River 102.0
END DESCRIPTION:
XS GIS Cut Line= 3
      1828374.99     13904775.02        1828825.       13904175.
        1828825.     13903775.02
#Sta/Elev= 30
  4262.5 2056.35  4326.1 2044.33  4369.8 2030.98  4455.2 2013.34  4469.8 2007.66
  4505.2  1999.7  4519.8 1993.98  4569.8 1983.26  4705.2 1970.12  4755.2 1961.46
  4762.5 1953.91  4782.6 1952.94  4826.1 1953.92  4840.6 1950.91    4849 1947.03
  4855.2 1947.95  4862.5 1944.31  4932.8 1941.55  4934.3 1940.55  4992.2 1941.55
  4997.8 1942.14  5022.5 1941.76  5042.5 1944.71  5052.5 1949.01  5062.5 1950.66
  5072.5 1976.01  5092.5 1991.89  5102.5  1994.1  5202.5 2006.99  5412.5 2021.05
#Mann= 5 ,-1 , 0
  4262.5      .1       0  4782.6    .035       0  4932.8     .05       0
  4992.2    .035       0  4997.8      .1       0
Bank Sta=4932.8,4992.2
XS Rating Curve= 0 ,0
Exp/Cntr=0.3,0.1

Type RM Length L Ch R = 1 ,71398   ,735,735,735
BEGIN DESCRIPTION:
South Fork Guadalupe River 101.0
END DESCRIPTION:
XS GIS Cut Line= 3
        1829175.     13904925.01        1829275.       13904325.
        1829325.       13903925.
#Sta/Elev= 30
  4392.2  2056.8  4425.2 2052.48    4486 2038.99  4541.7 2023.78  4574.7 2018.72
    4595  2012.6  4602.6  2008.5  4607.6    2008  4625.4 2000.08  4655.8 1991.97
  4663.4 1988.72  4668.5 1988.47  4724.2 1970.62  4790.1 1965.04  4828.1 1958.89
  4918.7 1953.82  4967.5  1943.7  4968.3 1941.33  4969.7 1940.33  5026.2 1940.33
  5027.7 1941.33    5078  1942.4  5101.3    1943  5118.9 1946.81  5131.5 1946.52
  5141.6 1968.68  5151.7 1976.48  5181.9 1983.99  5232.3 1990.96  5403.6 2007.58
#Mann= 5 ,-1 , 0
  4392.2      .1       0  4918.7    .035       0  4968.3    .035       0
  5027.7    .035       0    5078      .1       0
Bank Sta=4968.3,5027.7
XS Rating Curve= 0 ,0
Exp/Cntr=0.3,0.1