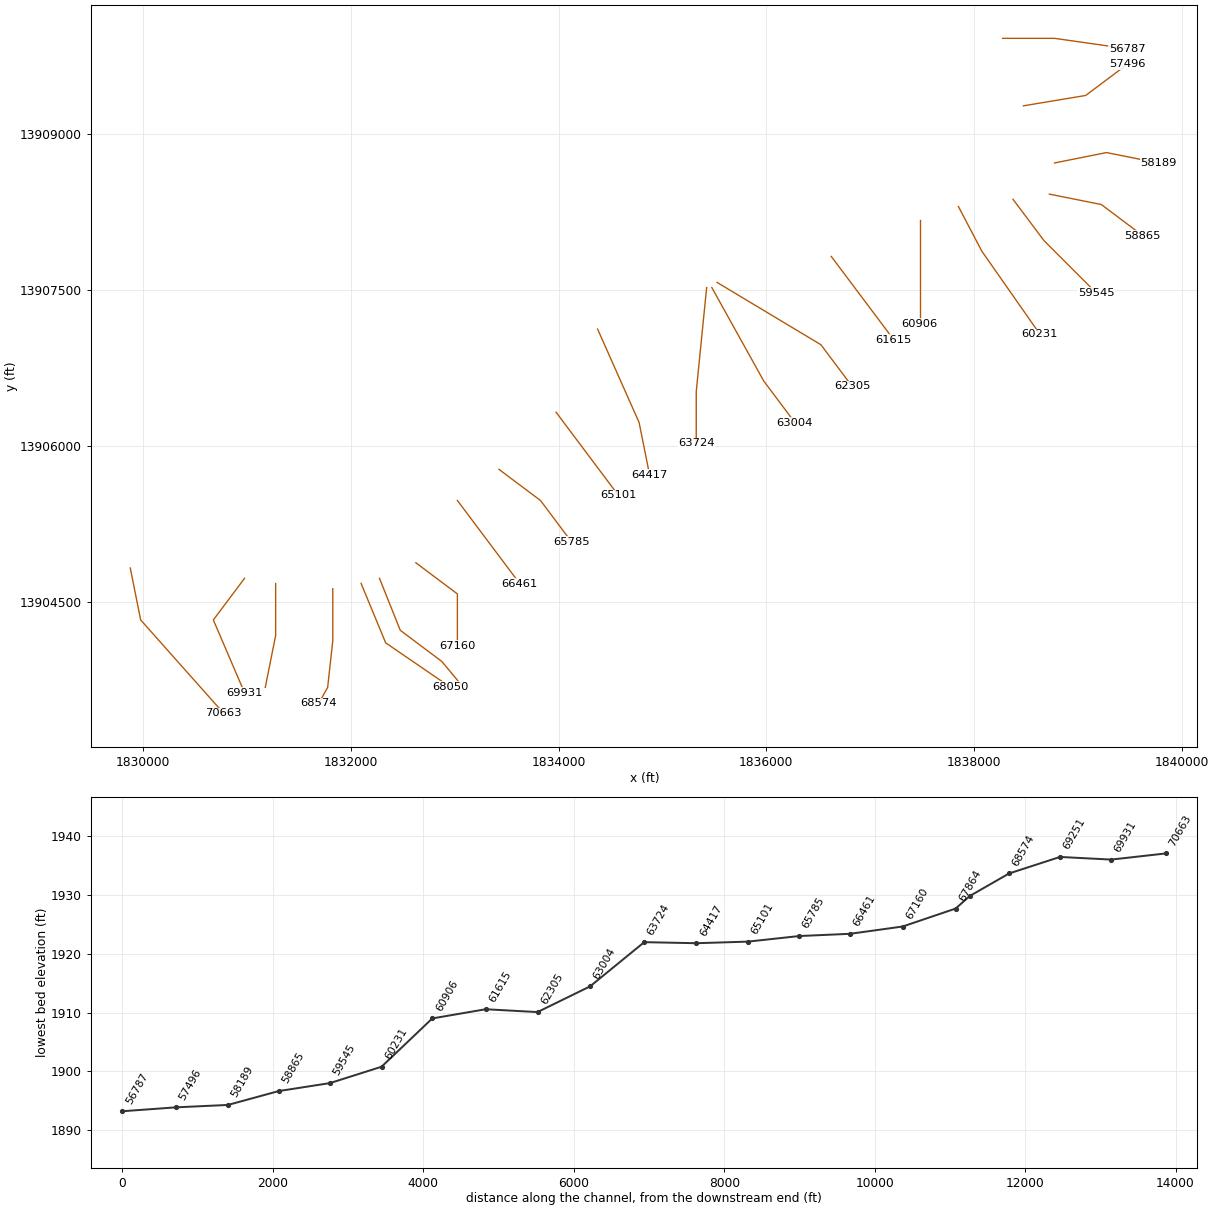
HEC-RAS study South Fork Guadalupe River.prj: South Fork Guadalupe River Base Level Engineering

--- South Fork Guadalupe River.g01 (geometry) --- (continued)

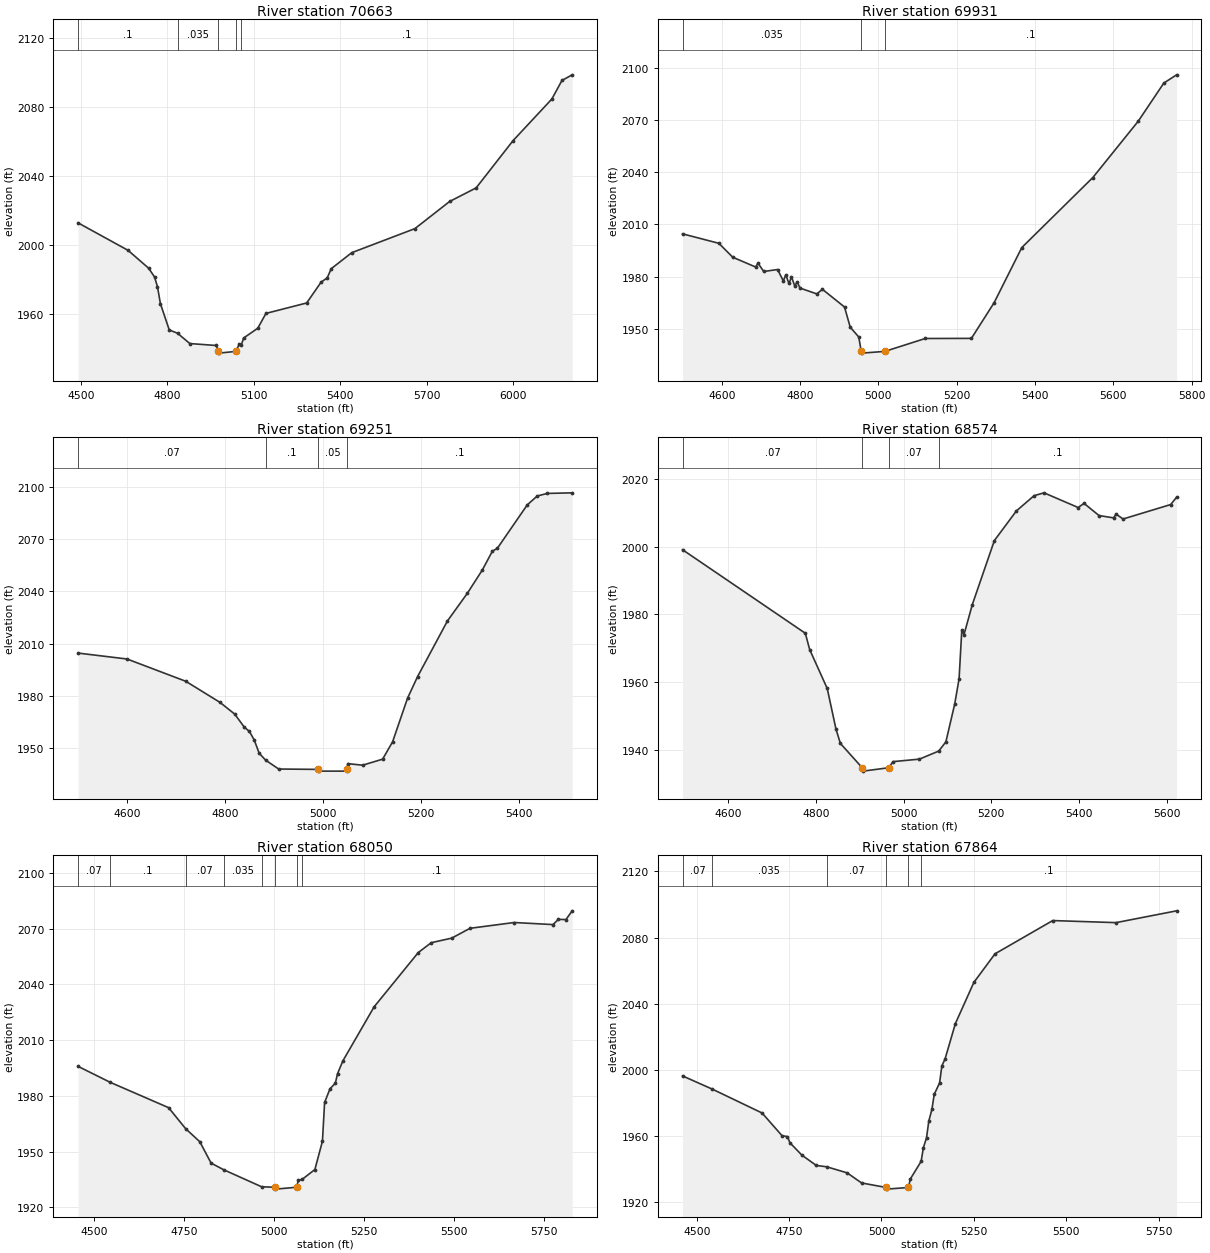
Type RM Length L Ch R = 1 ,70663   ,732,732,732
BEGIN DESCRIPTION:
South Fork Guadalupe River 100.0
END DESCRIPTION:
XS GIS Cut Line= 3
        1829875.     13904824.98        1829975.       13904325.
      1830774.97     13903425.03
#Sta/Elev= 30
  4490.1 2012.66  4663.4 1996.72  4734.8 1986.35  4755.2 1981.26  4765.4  1975.6
  4775.6 1965.75  4806.2 1950.54  4835.1 1948.58  4877.6 1942.61  4969.4 1941.48
    4977 1938.05  4978.5 1937.05  5037.2 1938.05  5049.7 1942.46  5056.3 1941.63
    5064 1945.79  5113.3  1951.5  5141.7 1960.11    5283 1966.17  5333.2 1978.31
  5354.1 1980.69  5368.3 1986.09  5439.4 1995.37  5658.5 2009.34  5778.9 2025.09
  5870.9 2032.98  5998.8 2060.39  6133.5 2084.57  6168.6 2095.36  6204.1 2098.62
#Mann= 5 ,-1 , 0
  4490.1      .1       0  4835.1    .035       0    4977    .035       0
  5037.2    .035       0  5056.3      .1       0
Bank Sta=4977,5037.2
XS Rating Curve= 0 ,0
Exp/Cntr=0.3,0.1

Type RM Length L Ch R = 1 ,69931   ,680,680,680
BEGIN DESCRIPTION:
South Fork Guadalupe River 99.0
END DESCRIPTION:
XS GIS Cut Line= 3
      1830975.03     13904725.04        1830675.       13904325.
      1830974.99     13903625.02
#Sta/Elev= 30
    4500 2004.56  4592.8 1999.12  4628.2 1991.12  4686.5 1985.51  4692.8 1987.69
  4707.3 1982.92  4742.8 1984.06  4757.3 1977.48  4763.6 1980.94  4771.9 1976.03
  4778.2 1979.86  4786.5 1974.66  4792.8 1976.89    4800 1973.39  4842.8 1970.05
  4857.3 1972.66  4913.6 1962.51  4928.2 1950.91    4950 1945.26  4956.3    1937
  4957.8    1936  5016.7    1937  5119.7 1944.41  5237.6 1944.47  5295.6 1964.97
  5366.3 1996.68  5547.7 2036.93  5663.7 2069.33    5729 2091.24  5761.6 2095.96
#Mann= 3 ,-1 , 0
    4500    .035       0  4956.3    .035       0  5016.7      .1       0
Bank Sta=4956.3,5016.7
XS Rating Curve= 0 ,0
Exp/Cntr=0.3,0.1

Type RM Length L Ch R = 1 ,69251   ,677,677,677
BEGIN DESCRIPTION:
South Fork Guadalupe River 98.0
END DESCRIPTION:
XS GIS Cut Line= 3
        1831275.     13904674.99        1831275.       13904175.
        1831175.       13903675.
#Sta/Elev= 30
  4499.6 2004.48  4599.6 2001.07  4719.6 1988.24  4789.6 1976.07  4819.6 1969.34
  4839.6 1961.66  4849.6 1959.39  4859.6  1954.4  4869.6 1946.82  4882.8 1942.78
  4909.6 1937.66  4989.8 1937.45  4991.3 1936.45  5048.7 1936.45  5050.2 1937.45
  5050.6 1940.77  5081.2 1939.87    5122 1943.35  5142.4 1953.35    5173 1978.52
  5193.4 1990.89  5254.5    2023  5295.3 2038.99  5325.9  2052.4  5346.3 2063.18
  5356.5 2064.86  5417.7 2089.91  5438.1 2095.02  5458.5 2096.49  5509.5 2096.84
#Mann= 4 ,-1 , 0
  4499.6     .07       0  4882.8      .1       0  4989.8     .05       0
  5050.2      .1       0
Bank Sta=4989.8,5050.2
XS Rating Curve= 0 ,0
Exp/Cntr=0.3,0.1

Type RM Length L Ch R = 1 ,68574   ,524,524,524
BEGIN DESCRIPTION:
South Fork Guadalupe River 97.0
END DESCRIPTION:
XS GIS Cut Line= 4
        1831825.     13904624.95        1831825.       13904125.
      1831775.88     13903675.72       1831690.8     13903522.92
#Sta/Elev= 30
  4495.8 1999.16  4775.8 1974.44  4785.8  1969.6  4825.8 1958.09  4845.8 1946.05
  4855.8 1941.84  4905.6 1934.64  4907.1 1933.64    4966 1934.64  4975.8 1936.45
    5036 1937.19    5080 1939.57  5096.4  1942.3  5116.5 1953.48  5126.5 1960.96
  5132.7 1975.37  5137.7 1974.01  5156.7 1982.92    5207 2001.87  5257.3 2010.65
  5297.5 2015.14  5320.2 2015.99  5398.1 2011.64  5411.5 2012.87  5445.6 2009.27
  5478.8 2008.58  5484.5 2009.69  5500.5 2008.25  5609.1 2012.52  5622.6 2014.69
#Mann= 4 ,-1 , 0
  4495.8     .07       0  4905.6    .033       0    4966     .07       0
    5080      .1       0
Bank Sta=4905.6,4966
XS Rating Curve= 0 ,0
Exp/Cntr=0.3,0.1

Type RM Length L Ch R = 1 ,68050   ,186,186,186
BEGIN DESCRIPTION:
South Fork Guadalupe River 96.1
END DESCRIPTION:
XS GIS Cut Line= 3
      1832097.36     13904677.05      1832334.32     13904104.18
      1832953.89     13903679.85
#Sta/Elev= 30
  4456.3  1995.9  4545.1 1987.34  4707.4 1973.66  4754.7 1962.34    4794 1955.32
  4825.3 1943.81  4860.2 1940.24  4965.3 1931.08  5001.8  1930.8  5003.3  1929.8
  5062.3  1930.8  5067.4 1934.45  5078.3 1935.11  5113.2 1940.34  5134.2  1955.6
  5140.2 1976.47  5155.1 1983.81  5170.1 1986.88  5176.1 1991.97    5191  1998.9
  5277.7    2028  5400.2 2057.22  5436.1 2062.51    5493 2064.97  5543.7 2070.26
  5666.3 2073.38  5773.9 2072.26  5788.8 2075.06  5809.8 2074.97  5827.2 2079.67
#Mann= 8 ,-1 , 0
  4456.3     .07       0  4545.1      .1       0  4754.7     .07       0
  4860.2    .035       0  4965.3     .07       0  5001.8     .05       0
  5062.3     .07       0  5078.3      .1       0
Bank Sta=5001.8,5062.3
XS Rating Curve= 0 ,0
Exp/Cntr=0.3,0.1

Type RM Length L Ch R = 1 ,67864   ,704,704,704
BEGIN DESCRIPTION:
South Fork Guadalupe River 96.0
END DESCRIPTION:
XS GIS Cut Line= 4
      1832275.01     13904724.98        1832475.       13904225.
        1832875.       13903925.      1833066.11      13903695.3
#Sta/Elev= 30
  4461.5 1996.21  4541.7 1988.25  4676.9 1973.76  4730.7 1960.05  4745.5 1959.48
  4752.3 1955.71  4784.6 1948.25  4823.6 1942.01  4851.7 1941.21  4907.1 1937.52
  4946.1 1931.42  5012.5 1928.68    5014 1927.68    5073 1928.68  5078.1 1933.84
  5107.3 1944.49  5113.5 1952.79  5121.9 1958.76  5128.1  1968.9  5136.5 1975.96
  5142.7 1985.02  5157.3    1992  5163.5 2002.36  5171.9 2006.36    5200 2027.88
    5250 2052.82  5307.3 2070.13  5463.5 2090.26  5634.7    2089  5798.8 2096.15
#Mann= 6 ,-1 , 0
  4461.5     .07       0  4541.7    .035       0  4851.7     .07       0
  5012.5     .05       0    5073     .07       0  5107.3      .1       0
Bank Sta=5012.5,5073
XS Rating Curve= 0 ,0
Exp/Cntr=0.3,0.1

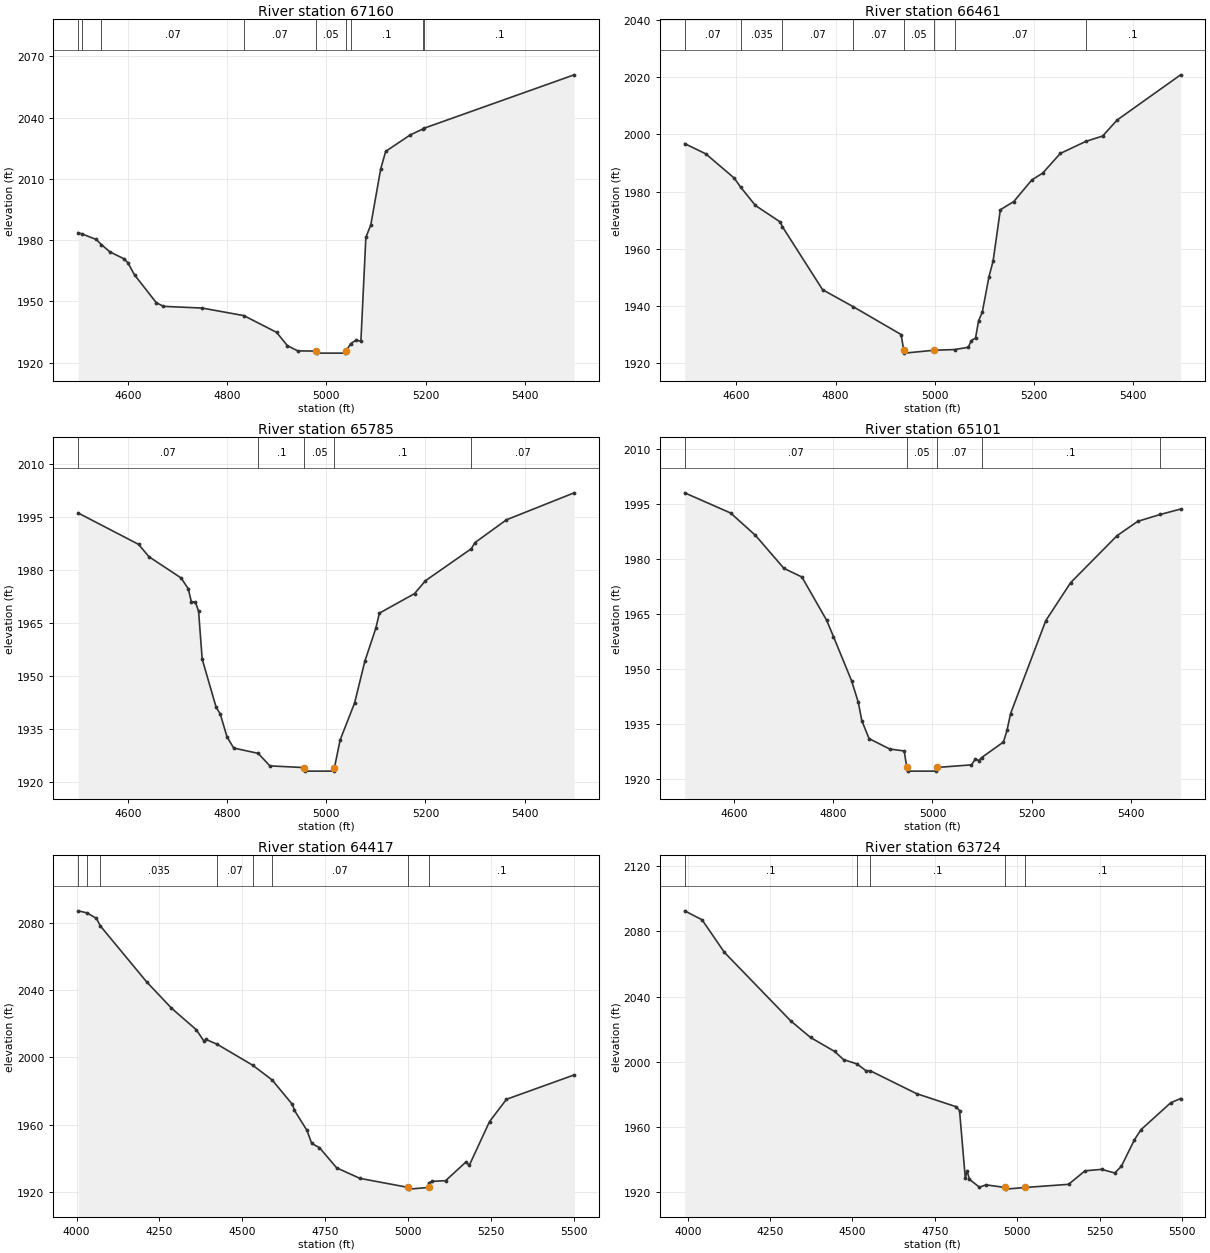
Type RM Length L Ch R = 1 ,67160   ,699,699,699
BEGIN DESCRIPTION:
South Fork Guadalupe River 95.0
END DESCRIPTION:
XS GIS Cut Line= 3
      1832625.02     13904874.99        1833025.       13904575.
        1833025.     13904074.98
#Sta/Elev= 30
  4499.5 1983.62  4507.2 1983.03  4535.9 1980.32  4546.3 1977.82    4563 1974.29
  4592.2 1970.81  4599.5 1968.94    4613    1963  4656.8 1949.38  4671.4 1947.55
  4749.5 1946.71  4833.5 1943.01  4899.5 1934.81  4921.4 1928.26  4942.2 1925.73
  4979.2 1925.63  4980.7 1924.63  5038.2 1924.63  5039.7 1925.63  5048.7 1929.21
  5059.5 1930.97  5069.5 1930.53  5079.5 1981.31  5089.5  1987.5  5109.5 2014.96
  5119.5  2023.5  5169.5 2031.62  5194.9 2034.49  5197.7  2034.9  5499.5 2060.99
#Mann= 9 ,-1 , 0
  4499.5     .07       0  4507.2      .1       0  4546.3     .07       0
  4833.5     .07       0  4979.2     .05       0  5039.7     .07       0
  5048.7      .1       0  5194.9    .035       0  5197.7      .1       0
Bank Sta=4979.2,5039.7
XS Rating Curve= 0 ,0
Exp/Cntr=0.3,0.1

Type RM Length L Ch R = 1 ,66461   ,676,676,676
BEGIN DESCRIPTION:
South Fork Guadalupe River 94.0
END DESCRIPTION:
XS GIS Cut Line= 3
      1833024.99     13905475.02        1833325.       13905075.
      1833624.99     13904675.02
#Sta/Elev= 30
  4495.6 1996.78  4538.3 1993.18  4595.6 1984.69  4608.4 1981.53  4638.3  1975.1
  4688.3 1969.33  4692.6 1967.69  4773.7  1945.6  4835.9 1939.61  4932.1 1929.89
  4937.2 1924.39  4938.7 1923.39  4997.7 1924.39  5039.7 1924.64  5067.5 1925.43
  5073.7 1927.81  5082.1 1928.69  5088.3  1934.8  5095.6 1937.65  5109.2 1950.17
  5117.5 1955.64  5132.1  1973.6  5159.2 1976.49  5195.6 1984.06  5217.5 1986.44
  5252.9 1993.32  5304.5 1997.56  5338.3 1999.42  5367.5 2005.03  5495.6 2020.87
#Mann= 8 ,-1 , 0
  4495.6     .07       0  4608.4    .035       0  4692.6     .07       0
  4835.9     .07       0  4937.2     .05       0  4997.7     .07       0
  5039.7     .07       0  5304.5      .1       0
Bank Sta=4937.2,4997.7
XS Rating Curve= 0 ,0
Exp/Cntr=0.3,0.1

Type RM Length L Ch R = 1 ,65785   ,684,684,684
BEGIN DESCRIPTION:
South Fork Guadalupe River 93.0
END DESCRIPTION:
XS GIS Cut Line= 3
      1833425.03     13905774.98        1833825.       13905475.
      1834125.02     13905074.97
#Sta/Elev= 30
  4499.8 1996.23  4621.6 1987.34  4642.5 1983.83  4707.1 1977.83  4721.6 1974.77
  4727.9  1971.1  4736.2 1970.95  4742.5 1968.37  4749.8 1954.77  4777.9 1941.14
  4786.2 1939.22  4799.8 1932.75  4813.3 1929.56  4862.7 1928.05  4886.2  1924.5
    4956 1924.01  4957.5 1923.01    5015 1923.01  5016.5 1924.01  5027.9 1931.84
  5057.1 1942.35  5077.9 1954.26  5099.8  1963.5  5107.1 1967.83  5177.9 1973.36
  5199.8 1977.01  5292.4  1986.1  5299.8 1987.84  5363.3 1994.31  5499.8 2001.96
#Mann= 5 ,-1 , 0
  4499.8     .07       0  4862.7      .1       0    4956     .05       0
  5016.5      .1       0  5292.4     .07       0
Bank Sta=4956,5016.5
XS Rating Curve= 0 ,0
Exp/Cntr=0.3,0.1

Type RM Length L Ch R = 1 ,65101   ,684,684,684
BEGIN DESCRIPTION:
South Fork Guadalupe River 92.0
END DESCRIPTION:
XS GIS Cut Line= 3
      1833975.03     13906324.96        1834275.       13905925.
      1834575.03     13905524.96
#Sta/Elev= 30
  4500.4 1997.99  4593.1 1992.48  4643.1 1986.39  4700.4  1977.4  4736.8 1975.02
  4786.8 1963.18  4800.4 1958.77  4836.8 1946.76  4850.4 1940.88  4857.6  1935.8
  4872.2 1930.94  4913.9 1928.09  4943.1 1927.56  4948.2 1923.06  4949.7 1922.06
  5007.3 1922.06  5008.8 1923.06  5078.5 1923.77  5086.8 1925.39  5093.1 1924.94
  5099.1 1925.75  5143.1    1930  5150.4 1933.23  5157.6 1937.78  5228.5 1963.11
  5278.5 1973.46  5372.2 1986.29  5413.9 1990.21  5459.2 1992.08  5500.4 1993.56
#Mann= 5 ,-1 , 0
  4500.4     .07       0  4948.2     .05       0  5008.8     .07       0
  5099.1      .1       0  5459.2     .07       0
Bank Sta=4948.2,5008.8
XS Rating Curve= 0 ,0
Exp/Cntr=0.3,0.1

Type RM Length L Ch R = 1 ,64417   ,693,693,693
BEGIN DESCRIPTION:
South Fork Guadalupe River 91.0
END DESCRIPTION:
XS GIS Cut Line= 3
        1834375.     13907125.01        1834775.       13906225.
        1834875.     13905724.99
#Sta/Elev= 30
  4005.1 2086.96  4031.2 2085.76  4059.8 2082.52  4071.8 2078.01    4211 2044.88
  4286.2  2029.2  4360.8 2016.43  4384.7 2009.47  4390.2 2010.65  4424.6  2007.7
  4530.7 1995.36  4589.5 1986.61  4650.8 1972.03  4656.9 1968.51  4694.5 1956.67
  4708.9 1948.91  4732.1 1946.43  4784.1 1934.42  4853.9 1928.19  5000.4 1922.79
  5001.9 1921.79  5061.1 1922.79  5061.4 1925.43  5071.6 1926.39  5112.4 1926.81
  5173.6 1937.88  5183.8  1935.9  5244.9 1961.91  5295.9 1975.11  5499.9 1989.57
#Mann= 8 ,-1 , 0
  4005.1    .035       0  4031.2     .07       0  4071.8    .035       0
  4424.6     .07       0  4530.7    .035       0  4589.5     .07       0
  5000.4     .05       0  5061.1      .1       0
Bank Sta=5000.4,5061.1
XS Rating Curve= 0 ,0
Exp/Cntr=0.3,0.1

Type RM Length L Ch R = 1 ,63724   ,720,720,720
BEGIN DESCRIPTION:
South Fork Guadalupe River 90.0
END DESCRIPTION:
XS GIS Cut Line= 3
        1835425.     13907524.99        1835325.       13906525.
        1835325.     13906024.98
#Sta/Elev= 30
  3990.8 2092.61  4043.6 2087.11  4111.4 2067.13  4312.4 2025.17  4372.7 2014.96
  4445.6 2006.42  4473.2 2001.36  4513.2 1998.77    4541 1994.64  4554.4  1994.5
  4694.3 1980.53  4814.9 1972.47  4824.9 1970.08  4842.5 1928.49  4847.5 1933.32
  4855.1 1927.96  4885.2 1923.16  4905.3  1924.6  4962.9 1922.97  4964.4 1921.97
  5023.6 1922.97  5155.8 1924.92  5205.8  1933.2  5255.8 1934.09  5295.8 1931.89
  5315.8  1935.9  5355.8 1952.31  5375.8 1958.47  5465.8 1974.94  5495.8 1977.53
#Mann= 5 ,-1 , 0
  3990.8      .1       0  4513.2     .07       0  4554.4      .1       0
  4962.9     .05       0  5023.6      .1       0
Bank Sta=4962.9,5023.6
XS Rating Curve= 0 ,0
Exp/Cntr=0.3,0.1

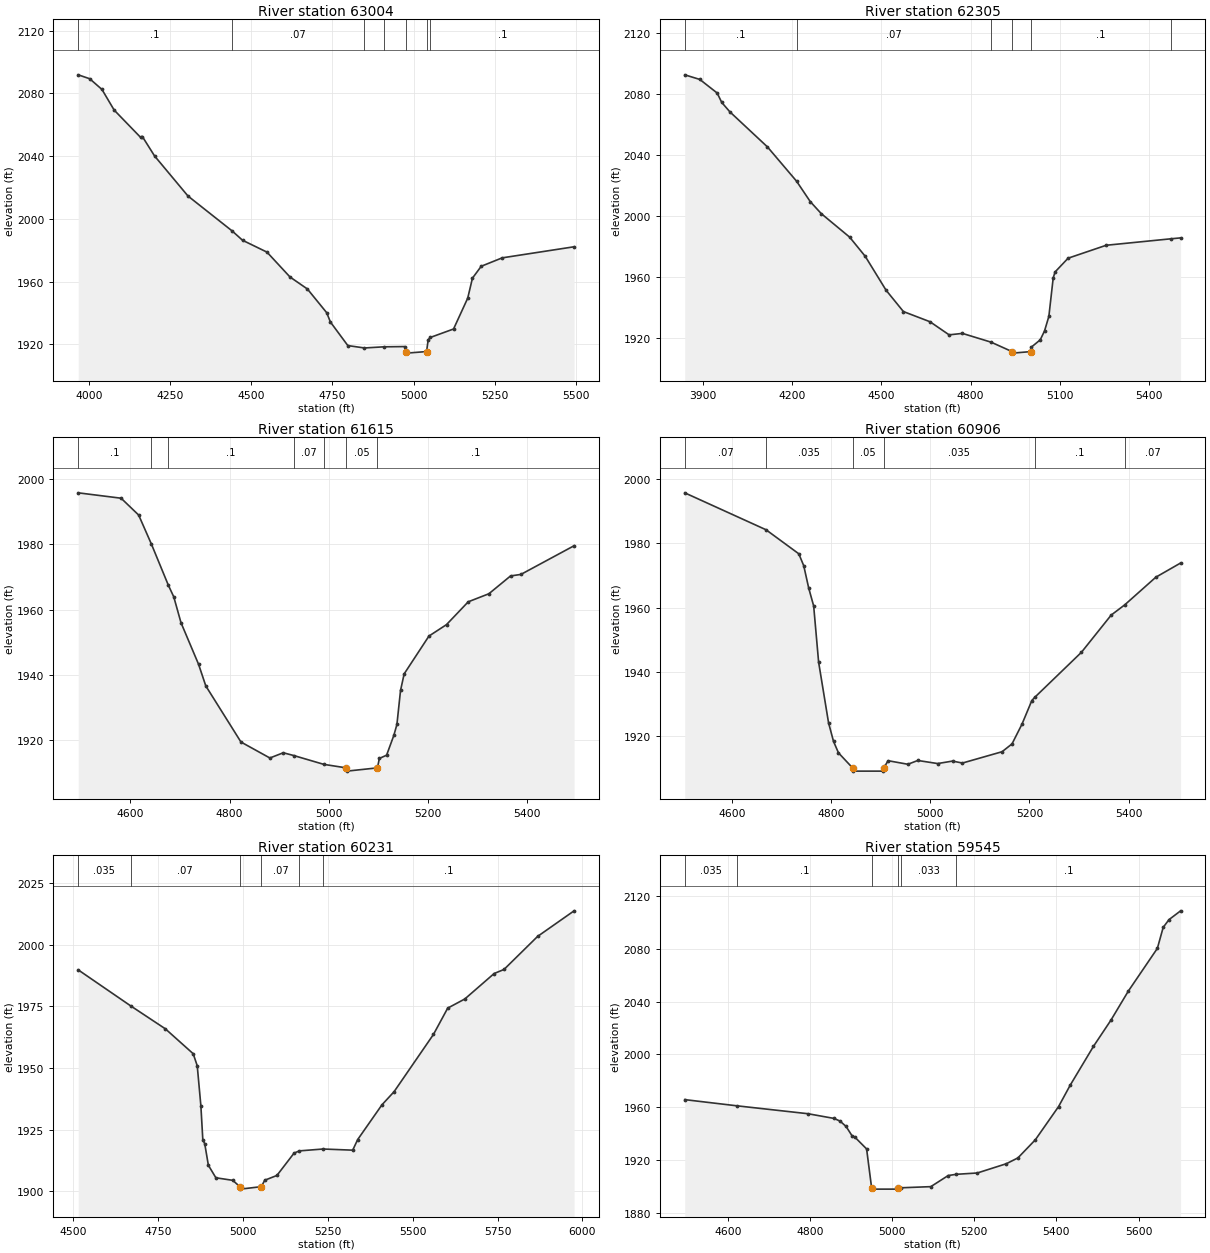
Type RM Length L Ch R = 1 ,63004   ,699,699,699
BEGIN DESCRIPTION:
South Fork Guadalupe River 89.0
END DESCRIPTION:
XS GIS Cut Line= 3
      1835475.01     13907524.98        1835975.       13906625.
      1836274.97     13906225.03
#Sta/Elev= 30
  3965.7 2091.83  4001.1 2089.34  4038.9 2082.52  4076.6 2069.36  4157.9 2052.01
  4163.6 2052.48  4201.3  2040.1  4304.3 2014.58  4440.4 1992.35  4472.5  1986.4
    4548 1978.82  4618.9 1962.99  4672.6 1955.34  4732.1 1940.23  4743.6 1934.29
  4797.3 1919.28  4848.6 1917.75  4908.5 1918.48  4972.4 1918.64  4977.3 1915.46
  4978.8 1914.46  5040.2 1915.46  5045.2 1923.03  5052.3 1924.49  5123.4 1929.84
  5167.1  1949.5  5181.7 1962.25  5208.8 1969.82  5273.4 1975.18  5495.2 1982.24
#Mann= 7 ,-1 , 0
  3965.7      .1       0  4440.4     .07       0  4848.6      .1       0
  4908.5     .07       0  4977.3     .05       0  5040.2     .07       0
  5052.3      .1       0
Bank Sta=4977.3,5040.2
XS Rating Curve= 0 ,0
Exp/Cntr=0.3,0.1

Type RM Length L Ch R = 1 ,62305   ,690,690,690
BEGIN DESCRIPTION:
South Fork Guadalupe River 88.0
END DESCRIPTION:
XS GIS Cut Line= 3
      1835524.97     13907575.02        1836525.       13906975.
      1836824.98     13906575.02
#Sta/Elev= 30
  3839.2 2092.74  3889.8 2089.72  3948.1 2080.81  3963.6  2074.6  3990.8 2068.46
  4117.2 2045.41  4214.8 2022.97    4261 2009.53  4297.9 2001.65  4393.2 1986.23
  4445.7 1973.62  4515.6 1951.41  4573.9 1937.38  4663.3 1930.69  4727.5 1922.09
  4772.2 1923.04  4868.6 1917.28    4939 1911.09  4940.5 1910.09  5001.9 1911.09
  5002.5 1913.82  5033.6 1918.79  5048.1 1924.63  5062.7 1934.23  5077.3 1959.47
  5083.6 1963.38  5127.3 1972.39  5255.4 1980.88  5472.6 1985.12  5505.4 1985.72
#Mann= 6 ,-1 , 0
  3839.2      .1       0  4214.8     .07       0  4868.6      .1       0
    4939     .05       0  5001.9      .1       0  5472.6     .07       0
Bank Sta=4939,5001.9
XS Rating Curve= 0 ,0
Exp/Cntr=0.3,0.1

Type RM Length L Ch R = 1 ,61615   ,709,709,709
BEGIN DESCRIPTION:
South Fork Guadalupe River 87.0
END DESCRIPTION:
XS GIS Cut Line= 3
      1836624.98     13907825.03        1836925.       13907425.
      1837224.98     13907025.03
#Sta/Elev= 30
  4494.7 1995.73  4581.2 1994.08  4616.6 1988.93  4642.4 1980.01  4676.7 1967.38
  4687.4  1963.9    4702 1955.98  4737.4 1943.27    4752 1936.64  4822.9 1919.48
  4881.2 1914.59  4908.3 1916.19  4929.6 1915.33    4990 1912.64  5035.1 1911.57
  5036.6 1910.57  5098.1 1911.57    5102 1914.45  5116.6 1915.45  5131.2 1921.51
  5137.4 1924.84  5144.7 1935.26    5152 1940.33    5202  1951.9  5237.4  1955.4
  5281.2 1962.38  5322.9 1964.85  5366.6  1970.3  5387.4 1970.76  5494.7 1979.54
#Mann= 7 ,-1 , 0
  4494.7      .1       0  4642.4     .07       0  4676.7      .1       0
  4929.6     .07       0    4990      .1       0  5035.1     .05       0
  5098.1      .1       0
Bank Sta=5035.1,5098.1
XS Rating Curve= 0 ,0
Exp/Cntr=0.3,0.1

Type RM Length L Ch R = 1 ,60906   ,675,675,675
BEGIN DESCRIPTION:
South Fork Guadalupe River 86.0
END DESCRIPTION:
XS GIS Cut Line= 3
        1837475.     13908174.97        1837475.       13907675.
        1837475.     13907174.97
#Sta/Elev= 30
  4504.8 1995.75  4668.6 1984.25  4734.8 1976.75  4744.8 1973.02  4754.8 1966.06
  4764.8 1960.49  4774.8 1942.95  4794.8 1924.09  4804.8 1918.29  4814.8 1914.71
  4843.3 1910.01  4844.8 1909.01  4904.8 1909.01  4906.3 1910.01  4914.8 1912.26
  4954.8 1911.15  4974.8 1912.33  5014.8 1911.37  5044.8 1912.14  5064.8 1911.53
  5144.8 1915.06  5164.8  1917.5  5184.8 1923.62  5204.8 1931.02  5210.7 1932.02
  5304.8 1946.05  5364.8 1957.65    5392 1960.82  5454.8 1969.45  5504.8 1973.88
#Mann= 6 ,-1 , 0
  4504.8     .07       0  4668.6    .035       0  4843.3     .05       0
  4906.3    .035       0  5210.7      .1       0    5392     .07       0
Bank Sta=4843.3,4906.3
XS Rating Curve= 0 ,0
Exp/Cntr=0.3,0.1

Type RM Length L Ch R = 1 ,60231   ,686,686,686
BEGIN DESCRIPTION:
South Fork Guadalupe River 85.0
END DESCRIPTION:
XS GIS Cut Line= 3
      1837849.47     13908305.06        1838075.       13907875.
      1838634.22     13907075.84
#Sta/Elev= 30
  4514.4 1989.83  4668.5 1975.26  4771.2 1965.89  4853.2 1955.78  4865.1 1950.88
  4875.8 1934.65  4881.5  1920.9  4887.2 1919.22  4897.9 1910.48    4920 1905.41
  4969.7 1904.37  4990.7  1901.8  4992.2  1900.8  5053.7  1901.8  5064.1 1904.42
  5099.8 1906.35  5150.4 1915.43  5166.1 1916.33  5235.9 1917.09  5323.1 1916.62
  5337.9 1920.95  5409.4 1935.05  5445.1 1940.38  5561.1 1963.63    5603  1974.3
  5653.5 1978.02  5739.9 1988.36  5768.9    1990    5868 2003.43  5975.4 2013.81
#Mann= 6 ,-1 , 0
  4514.4    .035       0  4668.5     .07       0  4990.7     .05       0
  5053.7     .07       0  5166.1    .033       0  5235.9      .1       0
Bank Sta=4990.7,5053.7
XS Rating Curve= 0 ,0
Exp/Cntr=0.3,0.1

Type RM Length L Ch R = 1 ,59545   ,680,680,680
BEGIN DESCRIPTION:
South Fork Guadalupe River 84.0
END DESCRIPTION:
XS GIS Cut Line= 3
        1838375.       13908375.        1838675.       13907975.
        1839175.       13907475.
#Sta/Elev= 30
  4495.4 1965.77  4623.2 1961.06  4795.4  1955.1  4858.9 1951.54  4873.5 1949.51
  4888.1 1945.47  4902.7 1938.39  4908.9 1937.57  4938.1 1928.46  4950.3 1899.02
  4951.8 1898.02  5011.9 1898.02  5013.4 1899.02  5022.2 1899.04  5094.4  1899.9
  5136.8 1908.32  5156.9 1909.25  5207.5 1910.23  5278.2 1917.24  5306.5 1921.67
  5348.9 1935.39  5405.5 1960.56  5433.8 1976.75  5490.4 2006.13  5532.8  2025.9
  5575.2 2047.92  5645.9 2080.28  5660.1 2096.19  5674.2 2102.03  5702.5 2108.69
#Mann= 6 ,-1 , 0
  4495.4    .035       0  4623.2      .1       0  4950.3     .05       0
  5013.4      .1       0  5022.2    .033       0  5156.9      .1       0
Bank Sta=4950.3,5013.4
XS Rating Curve= 0 ,0
Exp/Cntr=0.3,0.1

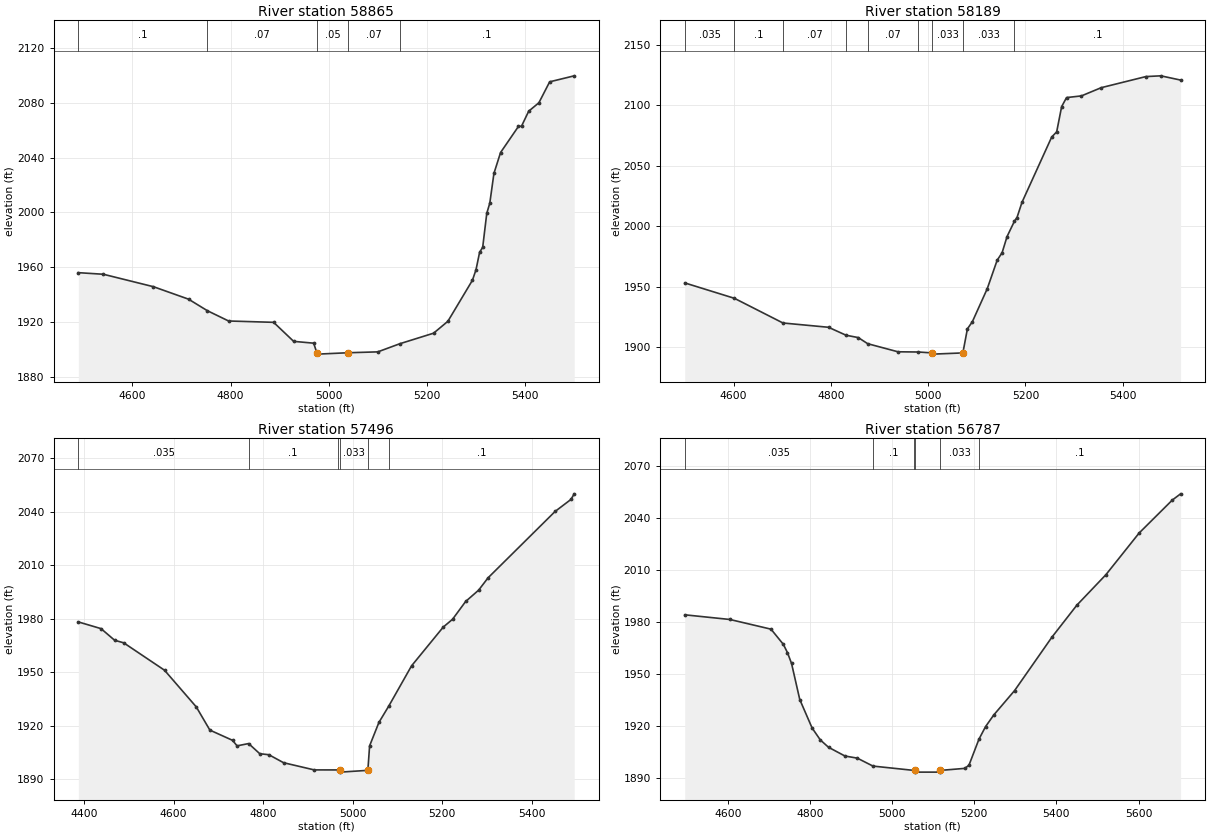
Type RM Length L Ch R = 1 ,58865   ,676,676,676
BEGIN DESCRIPTION:
South Fork Guadalupe River 83.0
END DESCRIPTION:
XS GIS Cut Line= 3
      1838724.98       13908425.        1839225.       13908325.
      1839624.98     13908025.01
#Sta/Elev= 30
  4490.1 1956.08  4541.1 1954.92  4643.1 1945.84  4714.5 1936.76  4752.9 1928.34
  4796.1 1920.84  4887.8 1919.86  4928.6 1905.98  4969.4 1904.66  4975.8 1897.67
  4977.3 1896.67  5038.9 1897.67    5100 1898.32  5144.9 1904.26  5213.6 1911.94
  5242.7 1920.62  5292.7 1950.55    5300 1958.23  5307.3 1970.93  5313.6 1974.56
  5321.9 1999.33  5328.1 2006.84  5336.5 2028.48    5350  2043.7  5386.5 2062.78
  5392.7 2062.93  5407.3 2073.85  5428.1 2080.01    5450 2095.27    5500 2099.64
#Mann= 5 ,-1 , 0
  4490.1      .1       0  4752.9     .07       0  4975.8     .05       0
  5038.9     .07       0  5144.9      .1       0
Bank Sta=4975.8,5038.9
XS Rating Curve= 0 ,0
Exp/Cntr=0.3,0.1

Type RM Length L Ch R = 1 ,58189   ,693,693,693
BEGIN DESCRIPTION:
South Fork Guadalupe River 82.0
END DESCRIPTION:
XS GIS Cut Line= 3
        1838775.       13908725.        1839275.       13908825.
        1839775.       13908725.
#Sta/Elev= 30
  4499.4 1953.21  4601.5 1940.48  4701.4 1920.06  4795.1 1916.51  4831.2 1909.93
  4856.3 1907.99  4875.7 1902.92  4937.9 1896.24  4979.5 1896.07  5008.3 1895.31
  5009.8 1894.31  5071.4 1895.31  5080.7 1915.21  5090.9 1921.11  5121.5 1948.39
  5141.9 1971.96  5152.1 1978.21  5162.3 1991.58  5177.4 2004.21  5182.7 2007.26
  5192.9 2019.79  5254.1 2073.88  5264.3 2078.12  5274.5 2098.98  5284.6 2106.47
  5315.2 2107.86    5356 2114.67  5447.8 2123.84  5478.4 2124.46  5519.2 2120.94
#Mann= 9 ,-1 , 0
  4499.4    .035       0  4601.5      .1       0  4701.4     .07       0
  4831.2      .1       0  4875.7     .07       0  4979.5    .033       0
  5008.3    .033       0  5071.4    .033       0  5177.4      .1       0
Bank Sta=5008.3,5071.4
XS Rating Curve= 0 ,0
Exp/Cntr=0.3,0.1

Type RM Length L Ch R = 1 ,57496   ,709,709,709
BEGIN DESCRIPTION:
South Fork Guadalupe River 81.0
END DESCRIPTION:
XS GIS Cut Line= 3
        1838475.       13909275.        1839075.       13909375.
      1839475.02     13909675.01
#Sta/Elev= 30
  4386.9 1978.15  4437.6 1974.39    4468 1967.87  4488.3 1966.43  4579.5 1951.06
  4650.5 1930.48  4680.9 1917.47  4731.6 1911.73  4741.7 1908.63  4767.5 1909.93
  4792.4 1904.22  4812.7 1903.67  4845.6 1899.18  4914.1 1895.15  4966.3 1895.13
  4970.9  1894.9  4972.4  1893.9    5034  1894.9  5037.9 1908.65  5058.7 1921.78
    5081 1931.07  5131.6  1953.5  5202.5 1975.26  5223.3 1979.64  5252.5 1989.61
  5281.6 1995.98  5302.5 2002.85  5452.5 2040.12  5487.9 2046.86  5495.2    2050
#Mann= 6 ,-1 , 0
  4386.9    .035       0  4767.5      .1       0  4966.3    .033       0
  4970.9    .033       0    5034    .033       0    5081      .1       0
Bank Sta=4970.9,5034
XS Rating Curve= 0 ,0
Exp/Cntr=0.3,0.1

Type RM Length L Ch R = 1 ,56787   ,690,690,690
BEGIN DESCRIPTION:
South Fork Guadalupe River 80.0
END DESCRIPTION:
XS GIS Cut Line= 3
      1838275.03       13909925.        1838775.       13909925.
      1839475.03       13909825.
#Sta/Elev= 30
  4495.4 1984.07  4605.4 1981.37  4705.4 1975.78  4735.4 1967.03  4745.4 1962.26
  4755.4 1955.99  4775.4 1935.16  4805.4 1918.74  4825.4 1911.84  4845.4 1907.59
  4885.4 1902.54  4915.4 1901.32  4953.6 1896.73    5053 1894.24  5054.7 1894.24
  5056.2 1893.24  5116.4 1893.24  5117.9 1894.24  5177.2 1895.41  5187.3 1897.25
  5211.5 1912.21  5227.7 1919.53  5247.9 1926.32  5298.4 1940.34  5389.3 1971.19
  5449.9 1989.63  5520.6 2007.22  5601.5 2031.29  5682.3 2050.33  5702.5 2053.92
#Mann= 6 ,-1 , 0
  4495.4    .035       0  4953.6      .1       0    5053    .033       0
  5054.7     .05       0  5117.9    .033       0  5211.5      .1       0
Bank Sta=5054.7,5117.9
XS Rating Curve= 0 ,0
Exp/Cntr=0.3,0.1