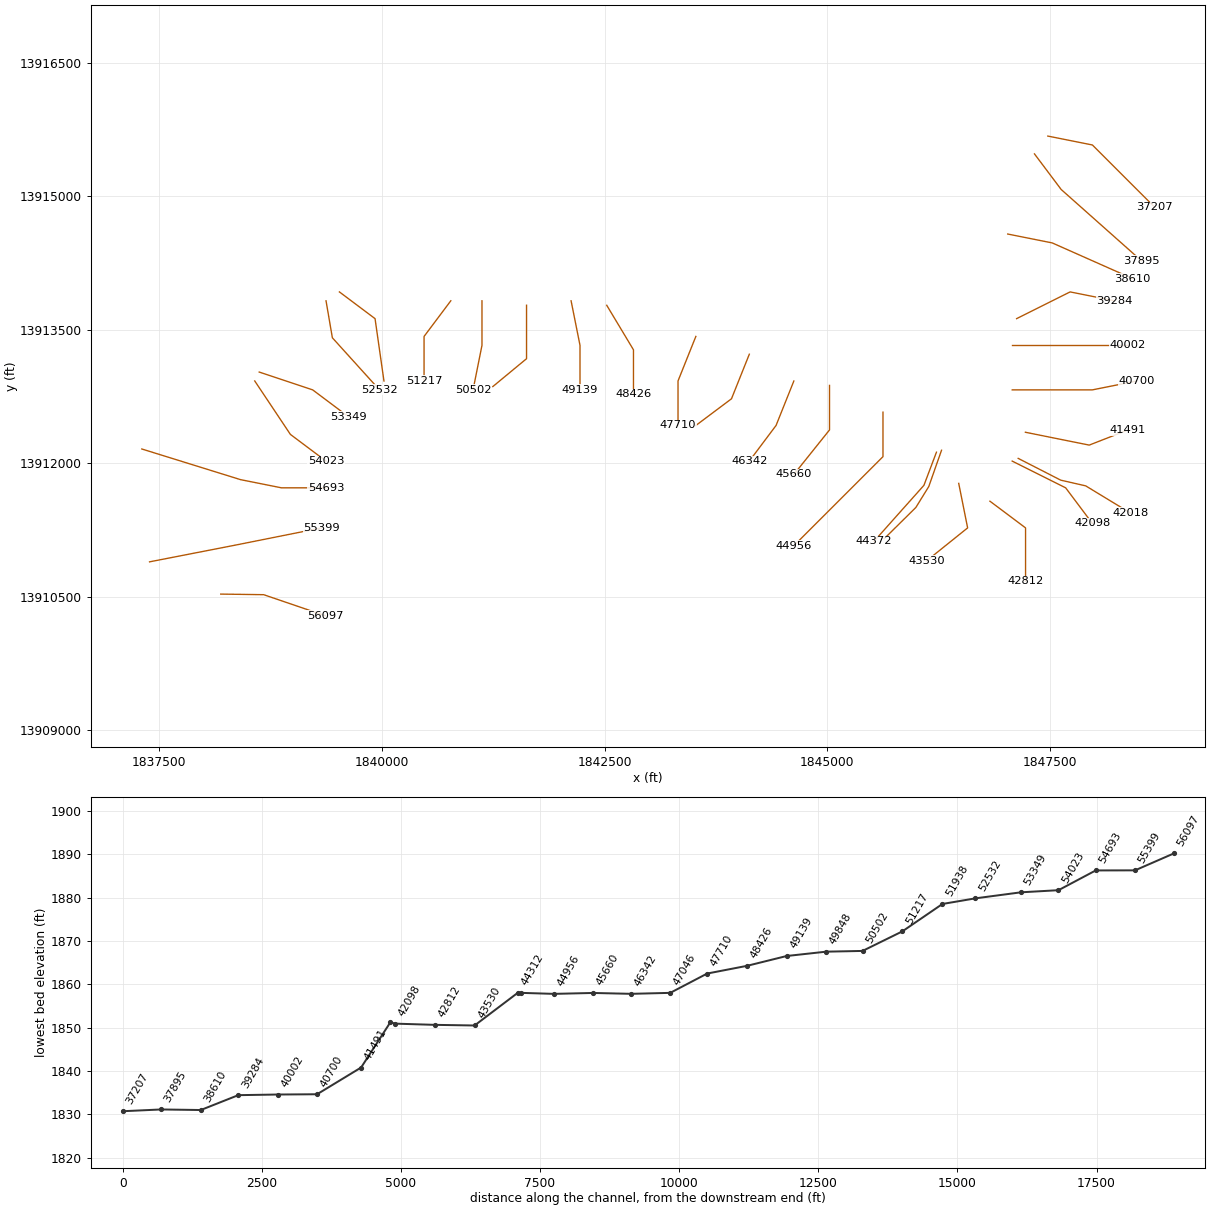
HEC-RAS study South Fork Guadalupe River.prj: South Fork Guadalupe River Base Level Engineering

--- South Fork Guadalupe River.g01 (geometry) --- (continued)

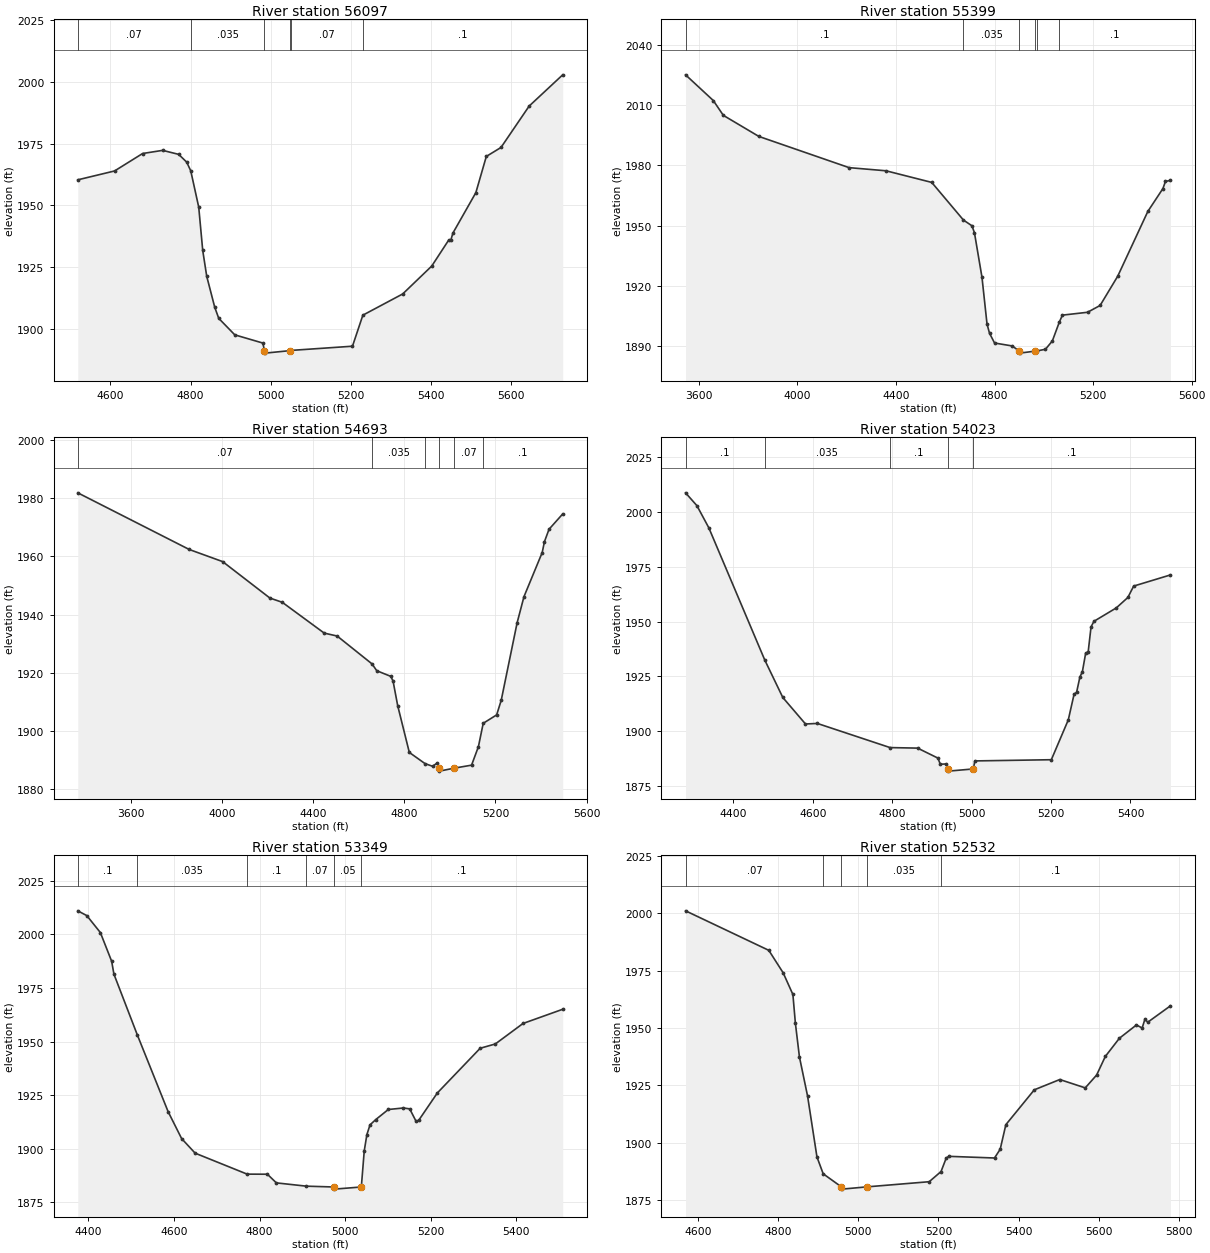
Type RM Length L Ch R = 1 ,56097   ,698,698,698
BEGIN DESCRIPTION:
South Fork Guadalupe River 79.0
END DESCRIPTION:
XS GIS Cut Line= 3
      1838193.21      13910531.6        1838675.       13910525.
      1839364.21     13910289.72
#Sta/Elev= 30
  4518.6 1960.39  4610.4 1963.98  4680.4 1971.05  4730.4 1972.32  4770.4  1970.7
  4790.4 1967.55  4800.5 1964.04  4820.4 1949.34  4830.4 1931.78  4840.4  1921.3
  4860.4 1908.76  4870.4 1904.28  4910.4 1897.61  4980.4 1894.29  4984.5 1891.21
    4986 1890.21  5047.7 1891.21  5049.9  1891.3  5204.1 1893.01    5230 1905.58
  5329.4 1914.17    5402 1925.49  5444.1 1935.96  5449.4 1935.91  5454.8 1938.85
    5512  1955.2  5538.1 1969.87  5574.7 1973.49    5645 1990.26  5728.7 2002.91
#Mann= 6 ,-1 , 0
  4518.6     .07       0  4800.5    .035       0  4984.5    .035       0
  5047.7    .035       0  5049.9     .07       0    5230      .1       0
Bank Sta=4984.5,5047.7
XS Rating Curve= 0 ,0
Exp/Cntr=0.3,0.1

Type RM Length L Ch R = 1 ,55399   ,706,706,706
BEGIN DESCRIPTION:
South Fork Guadalupe River 78.0
END DESCRIPTION:
XS GIS Cut Line= 4
      1837394.57     13910893.77      1838369.71     13911083.94
        1838825.       13911175.      1839324.98       13911275.
#Sta/Elev= 30
  3546.3 2025.28  3658.8 2012.45  3699.6 2005.04  3843.7 1994.52  4209.9 1978.93
  4359.6 1977.36  4545.2 1971.56  4674.1 1952.73  4708.4  1949.9  4718.6 1946.41
  4749.2 1924.13  4769.6 1900.82  4779.8  1896.2  4800.2 1891.35  4871.5 1889.89
  4901.1  1887.3  4902.6  1886.3  4964.3  1887.3  4973.7 1887.43  5006.7 1888.23
  5034.7 1892.38  5062.9 1901.76  5075.5 1905.27  5177.5  1906.7  5228.5 1910.11
  5299.9  1924.7  5422.2 1957.08  5483.4 1968.49  5493.6 1972.02    5514  1972.6
#Mann= 6 ,-1 , 0
  3546.3      .1       0  4674.1    .035       0  4901.1    .033       0
  4964.3    .035       0  4973.7    .033       0  5062.9      .1       0
Bank Sta=4901.1,4964.3
XS Rating Curve= 0 ,0
Exp/Cntr=0.3,0.1

Type RM Length L Ch R = 1 ,54693   ,670,670,670
BEGIN DESCRIPTION:
South Fork Guadalupe River 77.0
END DESCRIPTION:
XS GIS Cut Line= 4
      1837307.71     13912161.14      1838415.97     13911816.81
        1838875.       13911725.      1839374.97       13911725.
#Sta/Elev= 30
  3366.9 1981.81  3856.2 1962.36  4002.8  1958.2  4210.2 1945.69  4264.6 1944.23
  4448.6 1933.66  4505.5 1932.65  4658.3  1923.1  4679.4 1920.74  4740.6 1918.82
  4750.8 1917.22  4771.2 1908.75  4822.2  1892.7    4891 1888.87  4924.1 1887.95
  4944.5 1889.05  4953.1 1887.28  4954.6 1886.28  5017.6 1887.28  5095.5 1888.33
  5125.5 1894.67  5146.6  1902.7  5205.5 1905.58  5225.5 1910.54  5295.5 1937.23
  5325.5 1946.16  5405.5 1961.31  5415.5 1965.07  5435.5  1969.3  5495.5 1974.56
#Mann= 6 ,-1 , 0
  3366.9     .07       0  4658.3    .035       0    4891     .07       0
  4953.1     .05       0  5017.6     .07       0  5146.6      .1       0
Bank Sta=4953.1,5017.6
XS Rating Curve= 0 ,0
Exp/Cntr=0.3,0.1

Type RM Length L Ch R = 1 ,54023   ,674,674,674
BEGIN DESCRIPTION:
South Fork Guadalupe River 76.0
END DESCRIPTION:
XS GIS Cut Line= 3
      1838574.99     13912925.02        1838975.       13912325.
      1839374.98     13912025.02
#Sta/Elev= 30
  4279.6 2008.81  4308.2 2002.95  4338.2 1992.83  4479.1 1932.45  4524.5 1915.35
  4581.6 1903.25  4611.6 1903.49  4794.6 1892.47    4864 1892.23  4915.1 1887.67
  4921.1 1884.86  4936.1 1885.01  4939.9 1882.72  4941.4 1881.72  5004.4 1882.72
    5008 1886.38  5200.7 1886.93  5243.4 1905.12    5258 1916.86  5264.3 1917.71
  5272.6 1924.68  5278.9 1927.14  5287.2 1935.65  5293.4 1936.06  5300.7  1947.6
    5308 1950.14  5364.3 1956.26  5393.4 1961.02    5408 1966.22  5500.7 1971.32
#Mann= 5 ,-1 , 0
  4279.6      .1       0  4479.1    .035       0  4794.6      .1       0
  4939.9     .05       0  5004.4      .1       0
Bank Sta=4939.9,5004.4
XS Rating Curve= 0 ,0
Exp/Cntr=0.3,0.1

Type RM Length L Ch R = 1 ,53349   ,817,817,817
BEGIN DESCRIPTION:
South Fork Guadalupe River 75.0
END DESCRIPTION:
XS GIS Cut Line= 3
      1838624.96     13913025.01        1839225.       13912825.
        1839625.       13912525.
#Sta/Elev= 30
  4375.6 2010.95  4396.7 2008.72  4428.3 2000.83  4454.7 1987.44    4460 1981.44
  4514.9 1952.98  4586.5 1917.37  4618.1 1904.79  4649.7 1897.99  4771.1 1888.22
  4818.4 1888.18  4839.4 1884.14  4909.5 1882.61  4973.2 1882.23  4974.7 1881.23
  5037.8 1882.23  5044.6 1899.04  5050.8 1906.65  5058.1 1911.19  5071.6 1913.66
  5100.8 1918.35  5136.2 1919.05  5150.8 1918.64  5165.4 1912.94  5171.6 1913.24
  5215.4 1926.07  5315.4 1946.89  5350.8  1948.9  5415.4 1958.44  5508.1 1965.06
#Mann= 6 ,-1 , 0
  4375.6      .1       0  4514.9    .035       0  4771.1      .1       0
  4909.5     .07       0  4973.2     .05       0  5037.8      .1       0
Bank Sta=4973.2,5037.8
XS Rating Curve= 0 ,0
Exp/Cntr=0.3,0.1

Type RM Length L Ch R = 1 ,52532   ,594,594,594
BEGIN DESCRIPTION:
South Fork Guadalupe River 74.0
END DESCRIPTION:
XS GIS Cut Line= 3
      1839374.99     13913825.03      1839446.09     13913409.88
      1839975.03     13912824.97
#Sta/Elev= 30
  4569.2 2001.06  4776.9 1983.85  4812.7 1974.06    4837 1964.62  4843.2 1952.13
  4853.3 1937.43  4873.6 1920.39    4897 1893.87  4912.6 1886.51  4957.9 1880.84
  4959.4 1879.84  5022.8 1880.84  5177.1 1883.07  5206.6  1887.5  5219.6 1893.41
  5226.4 1894.12    5340  1893.4  5354.2 1897.22  5368.3 1907.91  5439.3  1923.1
  5502.9 1927.58  5566.4 1923.94  5594.8 1929.54  5616.4 1937.62  5651.6 1945.56
  5694.1 1951.35  5708.3 1950.02  5715.1 1953.75  5722.5 1952.56    5779 1959.69
#Mann= 5 ,-1 , 0
  4569.2     .07       0  4912.6    .035       0  4957.9    .035       0
  5022.8    .035       0  5206.6      .1       0
Bank Sta=4957.9,5022.8
XS Rating Curve= 0 ,0
Exp/Cntr=0.3,0.1

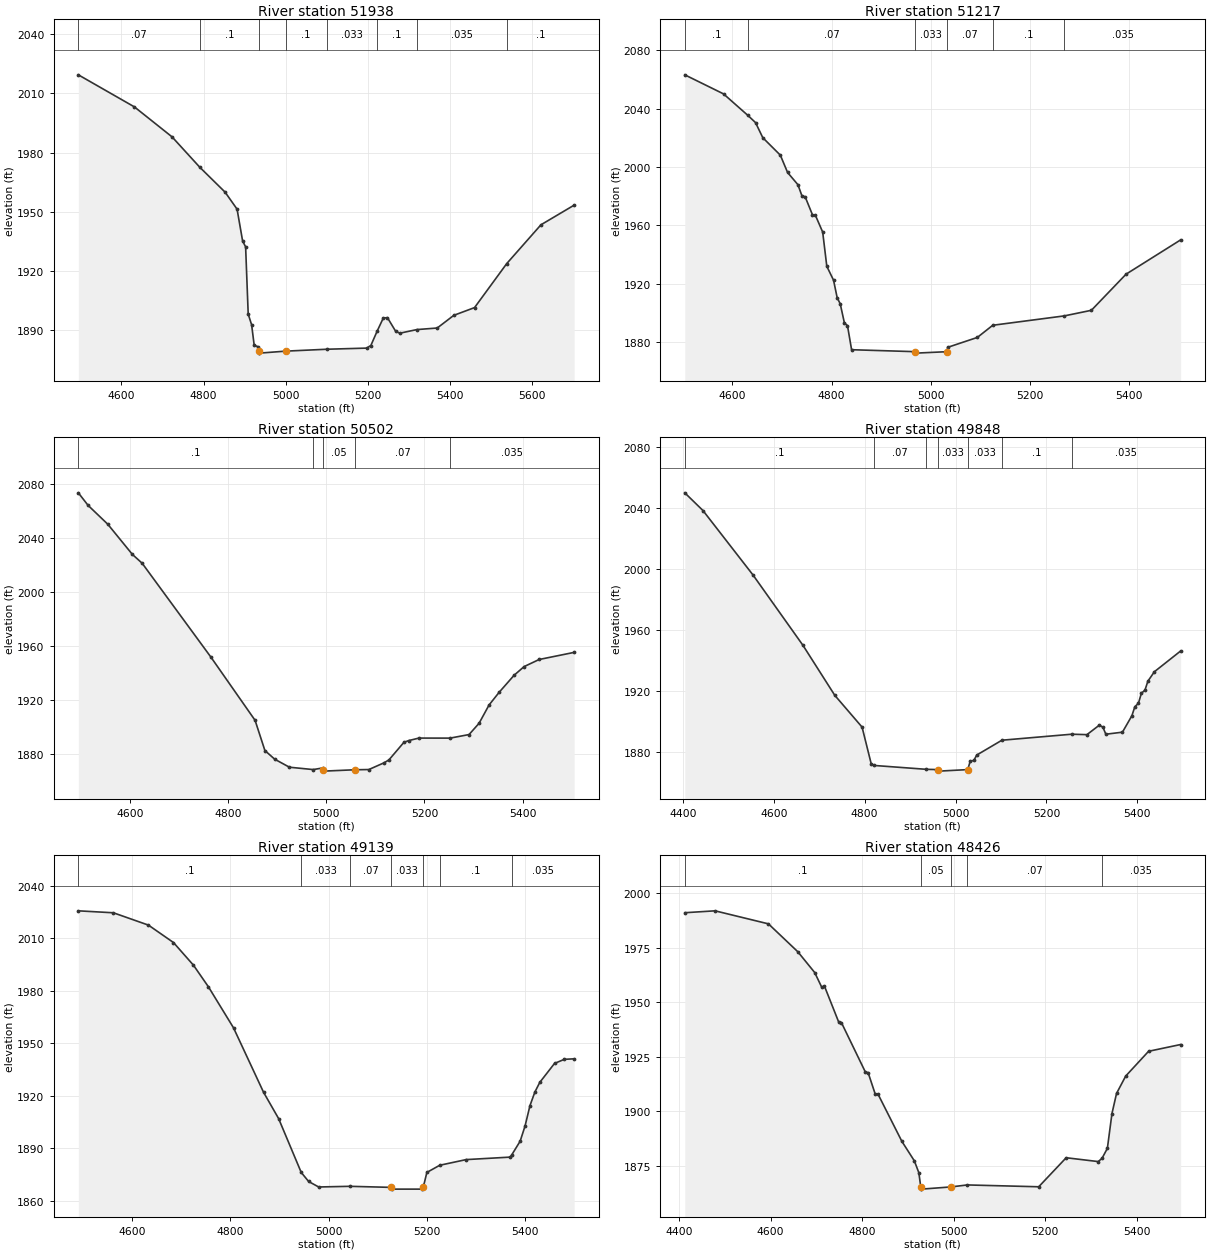
Type RM Length L Ch R = 1 ,51938   ,721,721,721
BEGIN DESCRIPTION:
South Fork Guadalupe River 73.0
END DESCRIPTION:
XS GIS Cut Line= 3
      1839524.96     13913925.03        1839925.       13913625.
      1840025.01     13912924.95
#Sta/Elev= 30
  4495.1 2019.41  4631.6 2003.18  4723.3    1988  4790.7 1972.65  4852.4 1960.03
  4881.6 1951.41  4895.1 1935.28  4902.4 1932.33  4908.7 1898.29    4917 1892.89
  4923.3 1882.47  4931.6 1881.89  4934.6 1879.54  4936.1 1878.54  4999.5 1879.54
  5100.4 1880.51  5197.2 1881.08  5207.3 1882.39  5223.3 1889.98  5237.6 1896.29
  5247.7 1896.49  5267.9 1889.53    5278 1888.64  5319.4 1890.46  5368.9 1891.25
  5409.3 1897.67  5459.8 1901.59  5538.1 1923.85  5621.4 1943.49  5702.3 1953.45
#Mann= 8 ,-1 , 0
  4495.1     .07       0  4790.7      .1       0  4934.6     .05       0
  4999.5      .1       0  5100.4    .033       0  5223.3      .1       0
  5319.4    .035       0  5538.1      .1       0
Bank Sta=4934.6,4999.5
XS Rating Curve= 0 ,0
Exp/Cntr=0.3,0.1

Type RM Length L Ch R = 1 ,51217   ,715,715,715
BEGIN DESCRIPTION:
South Fork Guadalupe River 72.0
END DESCRIPTION:
XS GIS Cut Line= 3
      1840774.99     13913824.98        1840475.       13913425.
        1840475.     13912924.98
#Sta/Elev= 30
  4503.9 2063.23    4582 2050.15    4631 2035.42  4646.6 2030.42  4661.2 2020.08
  4696.6 2008.08  4711.2  1996.2    4732 1987.84  4740.3 1980.04  4746.6 1979.55
  4761.2 1967.31  4767.4 1966.74    4782 1955.29  4790.3 1931.82  4803.9 1922.26
  4811.2 1910.27  4817.4 1906.03  4825.8 1892.93    4832 1891.07  4840.3 1874.55
  4968.3 1873.21  4969.8 1872.21  5033.3 1873.21  5033.9 1876.16  5093.9 1882.98
    5125 1891.33  5269.2 1897.76  5323.9  1901.6  5393.9 1926.41  5503.9 1949.93
#Mann= 6 ,-1 , 0
  4503.9      .1       0    4631     .07       0  4968.3    .033       0
  5033.3     .07       0    5125      .1       0  5269.2    .035       0
Bank Sta=4968.3,5033.3
XS Rating Curve= 0 ,0
Exp/Cntr=0.3,0.1

Type RM Length L Ch R = 1 ,50502   ,654,654,654
BEGIN DESCRIPTION:
South Fork Guadalupe River 71.0
END DESCRIPTION:
XS GIS Cut Line= 3
        1841125.     13913825.04        1841125.       13913325.
      1841025.01     13912825.05
#Sta/Elev= 30
  4495.1 2073.42  4515.1  2064.1  4555.1 2050.21  4605.1 2027.93  4625.1 2021.37
  4765.1 1951.99  4855.1 1905.25  4875.1 1882.92  4895.1 1876.51  4925.1 1870.59
  4973.5 1868.85  4992.6 1870.03  4993.2  1868.7  4994.7  1867.7  5058.2  1868.7
  5086.9 1868.88  5117.5 1873.81  5127.7 1875.98  5158.3 1889.01  5168.5 1890.33
  5188.9 1892.13  5252.3  1892.1  5290.9 1894.73  5311.3 1903.05  5331.7  1916.6
  5352.1 1925.92  5382.7 1938.57  5403.1 1944.98  5433.7 1950.22    5505 1955.48
#Mann= 5 ,-1 , 0
  4495.1      .1       0  4973.5     .07       0  4993.2     .05       0
  5058.2     .07       0  5252.3    .035       0
Bank Sta=4993.2,5058.2
XS Rating Curve= 0 ,0
Exp/Cntr=0.3,0.1

Type RM Length L Ch R = 1 ,49848   ,709,709,709
BEGIN DESCRIPTION:
South Fork Guadalupe River 70.0
END DESCRIPTION:
XS GIS Cut Line= 3
        1841625.     13913775.01        1841625.       13913175.
      1841246.79     13912862.22
#Sta/Elev= 30
  4404.3 2049.94  4444.3 2038.32  4554.3 1996.11  4664.3 1949.96  4734.3  1917.2
  4794.3 1896.38  4814.3 1872.45  4820.2 1871.26  4935.9 1868.71  4961.8 1868.53
  4963.3 1867.53  5026.8 1868.53  5032.3  1874.1  5040.1 1874.51  5046.6 1878.07
  5101.9 1887.79  5255.7 1891.73    5289 1891.44  5316.3 1897.67  5324.1 1896.33
  5330.6 1891.72  5367.1 1893.06  5387.9 1903.84  5394.4 1909.76  5402.3 1911.99
  5408.8 1918.59  5416.6 1920.59  5423.1  1926.5  5437.4 1932.68  5495.1 1946.27
#Mann= 7 ,-1 , 0
  4404.3      .1       0  4820.2     .07       0  4935.9    .033       0
  4961.8    .033       0  5026.8    .033       0  5101.9      .1       0
  5255.7    .035       0
Bank Sta=4961.8,5026.8
XS Rating Curve= 0 ,0
Exp/Cntr=0.3,0.1

Type RM Length L Ch R = 1 ,49139   ,713,713,713
BEGIN DESCRIPTION:
South Fork Guadalupe River 69.0
END DESCRIPTION:
XS GIS Cut Line= 3
        1842125.     13913824.99        1842225.       13913325.
        1842225.     13912824.99
#Sta/Elev= 30
  4490.2 2025.83  4561.6 2024.71    4633 2017.65    4684 2007.68  4724.7 1994.71
  4755.3 1982.28  4806.3 1958.85  4867.5 1921.95  4898.1 1906.93  4944.2 1876.08
  4959.3  1870.9  4979.7 1867.76  5043.3 1868.14  5127.5 1867.53    5129 1866.53
  5191.2 1866.53  5192.7 1867.53  5200.1 1876.09  5226.3 1880.19  5280.1 1883.43
  5370.1 1884.86  5373.2 1886.24  5390.1 1893.97  5400.1 1902.68  5410.1 1914.33
  5420.1 1922.11  5430.1 1927.64  5460.1 1938.48  5480.1 1940.83  5500.1 1941.12
#Mann= 7 ,-1 , 0
  4490.2      .1       0  4944.2    .033       0  5043.3     .07       0
  5127.5    .033       0  5192.7     .07       0  5226.3      .1       0
  5373.2    .035       0
Bank Sta=5127.5,5192.7
XS Rating Curve= 0 ,0
Exp/Cntr=0.3,0.1

Type RM Length L Ch R = 1 ,48426   ,716,716,716
BEGIN DESCRIPTION:
South Fork Guadalupe River 68.0
END DESCRIPTION:
XS GIS Cut Line= 3
      1842525.01     13913774.99        1842825.       13913275.
        1842825.     13912774.98
#Sta/Elev= 30
  4412.5 1991.08  4478.6 1991.95  4595.2 1985.97  4659.3 1973.19  4696.3 1963.63
  4711.8 1956.81  4717.6 1957.38  4748.7 1940.91  4754.6 1940.68    4807 1917.96
  4812.9 1917.74  4828.4 1907.91  4834.3 1907.95  4886.7 1886.17  4913.9 1877.25
  4923.7 1871.82    4928 1865.26  4929.5 1864.26  4993.2 1865.26  5029.7 1866.18
  5185.6 1865.34  5245.6 1878.66  5315.6  1876.9  5323.9 1878.39  5335.6 1882.97
  5345.6 1898.92  5355.6 1908.16  5375.6 1916.13  5425.6  1927.5  5495.6 1930.61
#Mann= 5 ,-1 , 0
  4412.5      .1       0    4928     .05       0  4993.2      .1       0
  5029.7     .07       0  5323.9    .035       0
Bank Sta=4928,4993.2
XS Rating Curve= 0 ,0
Exp/Cntr=0.3,0.1

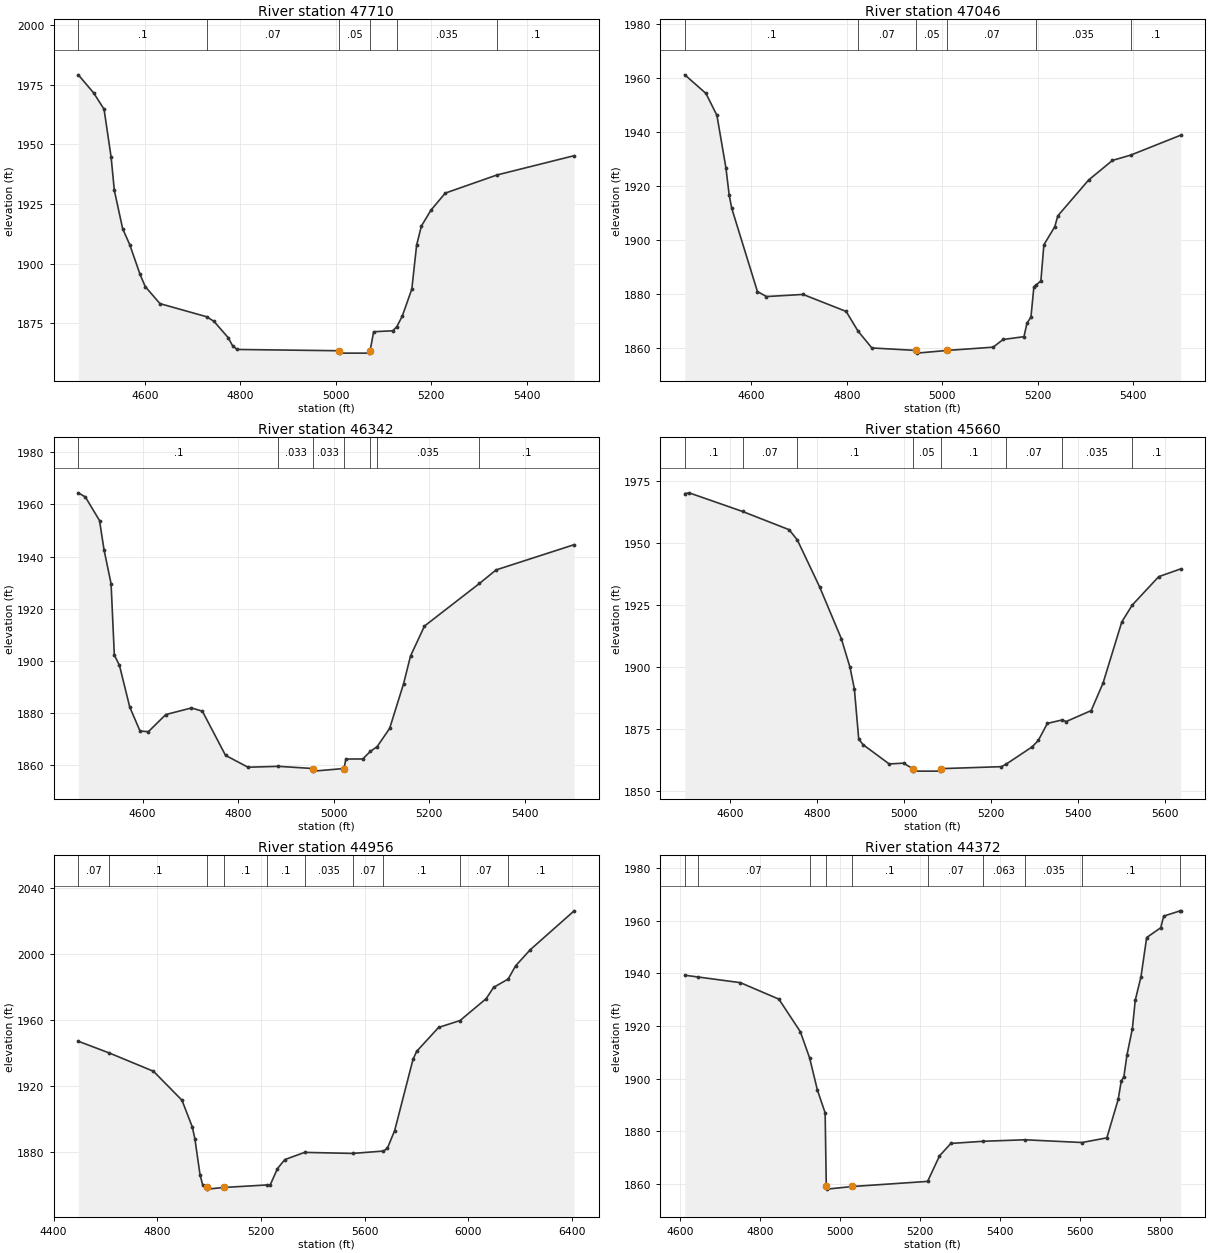
Type RM Length L Ch R = 1 ,47710   ,664,664,664
BEGIN DESCRIPTION:
South Fork Guadalupe River 67.0
END DESCRIPTION:
XS GIS Cut Line= 3
      1843525.01     13913425.03        1843325.       13912925.
        1843325.     13912424.95
#Sta/Elev= 30
  4460.8 1979.18  4493.1 1971.54  4514.7 1964.75  4529.5 1944.63  4536.2 1930.75
  4553.7 1914.62  4568.5 1907.96  4590.1 1895.49  4600.9  1890.4  4631.8 1883.24
  4729.9 1877.72  4744.9 1875.81  4774.5 1869.03  4783.9 1865.58  4793.4 1864.02
  5006.7 1863.48  5008.2 1862.48  5070.5 1862.48    5072 1863.48  5079.4 1871.45
  5119.4 1871.86  5127.9 1873.55  5139.4 1878.02  5159.4 1889.39  5169.4 1907.76
  5179.4 1915.78  5199.4 1922.42  5229.4 1929.58  5337.8 1937.19  5499.4 1945.28
#Mann= 6 ,-1 , 0
  4460.8      .1       0  4729.9     .07       0  5006.7     .05       0
    5072     .07       0  5127.9    .035       0  5337.8      .1       0
Bank Sta=5006.7,5072
XS Rating Curve= 0 ,0
Exp/Cntr=0.3,0.1

Type RM Length L Ch R = 1 ,47046   ,704,704,704
BEGIN DESCRIPTION:
South Fork Guadalupe River 66.0
END DESCRIPTION:
XS GIS Cut Line= 3
      1844125.01     13913225.01        1843925.       13912725.
      1843525.03     13912425.02
#Sta/Elev= 30
  4460.9 1961.24  4505.3 1954.33  4528.2  1946.2  4547.1 1926.66  4553.8 1916.72
  4559.2 1911.75    4613 1880.87  4631.9    1879  4708.6 1879.79  4798.8 1873.49
  4823.7  1866.2  4852.7 1859.94  4945.2 1859.02  4946.7 1858.02  5010.5 1859.02
  5106.7 1860.23  5127.6 1863.08  5171.3 1864.12  5177.6 1869.15  5185.9 1871.37
  5192.1 1882.68    5196 1883.18  5206.7 1884.81    5213 1898.19  5235.9 1904.94
  5242.1 1908.93  5306.7 1922.23  5356.7 1929.51  5394.8 1931.46  5499.4 1938.84
#Mann= 6 ,-1 , 0
  4460.9      .1       0  4823.7     .07       0  4945.2     .05       0
  5010.5     .07       0    5196    .035       0  5394.8      .1       0
Bank Sta=4945.2,5010.5
XS Rating Curve= 0 ,0
Exp/Cntr=0.3,0.1

Type RM Length L Ch R = 1 ,46342   ,682,682,682
BEGIN DESCRIPTION:
South Fork Guadalupe River 65.0
END DESCRIPTION:
XS GIS Cut Line= 3
      1844624.99     13912924.98        1844425.       13912425.
        1844125.       13912025.
#Sta/Elev= 30
  4465.3 1964.46  4480.1 1962.85  4509.7 1953.83  4519.1 1942.65  4533.9 1929.63
  4540.7 1902.31  4551.4 1898.34    4573 1882.36  4594.5 1873.17    4612 1872.91
  4648.4 1879.48  4702.2 1882.01  4725.1 1880.78  4773.6 1863.85  4820.7 1859.29
  4884.1 1859.64  4956.3  1858.8  4957.8  1857.8  5021.7  1858.8  5025.7 1862.43
  5061.1 1862.46  5076.7 1865.34    5091 1867.16  5117.3 1874.16  5146.5 1891.28
  5161.1 1901.95  5190.3  1913.4  5305.4 1929.72  5340.3 1934.92  5503.8 1944.59
#Mann= 7 ,-1 , 0
  4465.3      .1       0  4884.1    .033       0  4956.3    .033       0
  5021.7    .033       0  5076.7     .07       0    5091    .035       0
  5305.4      .1       0
Bank Sta=4956.3,5021.7
XS Rating Curve= 0 ,0
Exp/Cntr=0.3,0.1

Type RM Length L Ch R = 1 ,45660   ,704,704,704
BEGIN DESCRIPTION:
South Fork Guadalupe River 64.0
END DESCRIPTION:
XS GIS Cut Line= 3
        1845025.     13912875.01        1845025.       13912375.
      1844625.01     13911875.02
#Sta/Elev= 30
  4495.6 1969.81  4505.6 1970.12  4628.4 1962.61  4735.6 1955.26  4754.6 1951.07
  4805.6 1932.25  4855.6 1911.37  4875.6 1899.78  4885.6 1891.08  4895.6  1870.9
  4905.6 1868.67  4965.6  1860.9  4998.8 1861.21  5019.7    1859  5021.2    1858
  5083.6    1858  5085.1    1859  5223.7  1859.8  5234.2 1860.76  5294.2 1867.75
  5308.6 1870.37  5329.4 1877.22  5363.6 1878.63  5372.6 1877.97  5430.2 1882.39
  5457.4 1893.44  5500.7 1918.16  5524.7 1924.91  5585.5 1936.35  5635.9 1939.46
#Mann= 8 ,-1 , 0
  4495.6      .1       0  4628.4     .07       0  4754.6      .1       0
  5019.7     .05       0  5085.1      .1       0  5234.2     .07       0
  5363.6    .035       0  5524.7      .1       0
Bank Sta=5019.7,5085.1
XS Rating Curve= 0 ,0
Exp/Cntr=0.3,0.1

Type RM Length L Ch R = 1 ,44956   ,584,584,584
BEGIN DESCRIPTION:
South Fork Guadalupe River 63.0
END DESCRIPTION:
XS GIS Cut Line= 3
        1845625.     13912574.99        1845625.       13912075.
        1844625.       13911075.
#Sta/Elev= 30
  4495.2  1947.3  4614.8 1940.19  4785.2 1929.14  4895.2 1911.64  4935.2 1895.39
  4945.2 1888.25  4965.2 1866.34  4975.2 1860.43  4990.8 1858.79  4992.3 1857.79
  5056.2 1858.79  5225.2 1860.34  5235.6 1860.21  5263.9  1870.2  5292.2 1875.66
  5368.9 1880.03  5554.6 1879.41  5673.3 1880.84  5688.2 1882.48  5716.4 1893.21
  5787.2 1936.29  5801.3 1941.19  5886.1 1955.67  5968.8 1959.83    6070 1973.13
  6098.3  1979.9  6154.7 1984.96  6183.1 1992.91  6239.7 2002.68  6409.4 2026.25
#Mann= 10 ,-1 , 0
  4495.2     .07       0  4614.8      .1       0  4990.8     .05       0
  5056.2      .1       0  5225.2      .1       0  5368.9    .035       0
  5554.6     .07       0  5673.3      .1       0  5968.8     .07       0
  6154.7      .1       0
Bank Sta=4990.8,5056.2
XS Rating Curve= 0 ,0
Exp/Cntr=0.3,0.1

Type RM Length L Ch R = 1 ,44372   ,60,60,60
BEGIN DESCRIPTION:
South Fork Guadalupe River 62.0
END DESCRIPTION:
XS GIS Cut Line= 3
      1846224.99     13912124.98      1846084.64     13911753.18
      1845525.01     13911125.02
#Sta/Elev= 30
  4612.5 1939.34  4644.4 1938.69  4751.4 1936.51  4847.6 1930.24  4901.1 1917.88
  4924.3 1907.91  4943.8 1895.67  4963.1 1887.01    4966 1859.02  4967.5 1858.02
  5031.4 1859.02  5219.1 1860.96  5248.8 1870.65  5277.2 1875.39  5357.7 1876.21
  5462.1 1876.78    5605 1875.74  5666.9 1877.52  5695.3 1892.16  5702.8 1899.04
  5709.5 1900.82    5717 1908.88  5730.7 1919.08  5737.9 1929.88  5752.1  1938.7
  5766.4 1953.67  5801.5 1957.39    5809 1961.82  5850.1 1963.82  5851.2 1963.82
#Mann= 10 ,-1 , 0
  4612.5      .1       0  4644.4     .07       0  4924.3      .1       0
    4966     .05       0  5031.4      .1       0  5219.1     .07       0
  5357.7    .063       0  5462.1    .035       0    5605      .1       0
  5850.1     .07       0
Bank Sta=4966,5031.4
XS Rating Curve= 0 ,0
Exp/Cntr=0.3,0.1

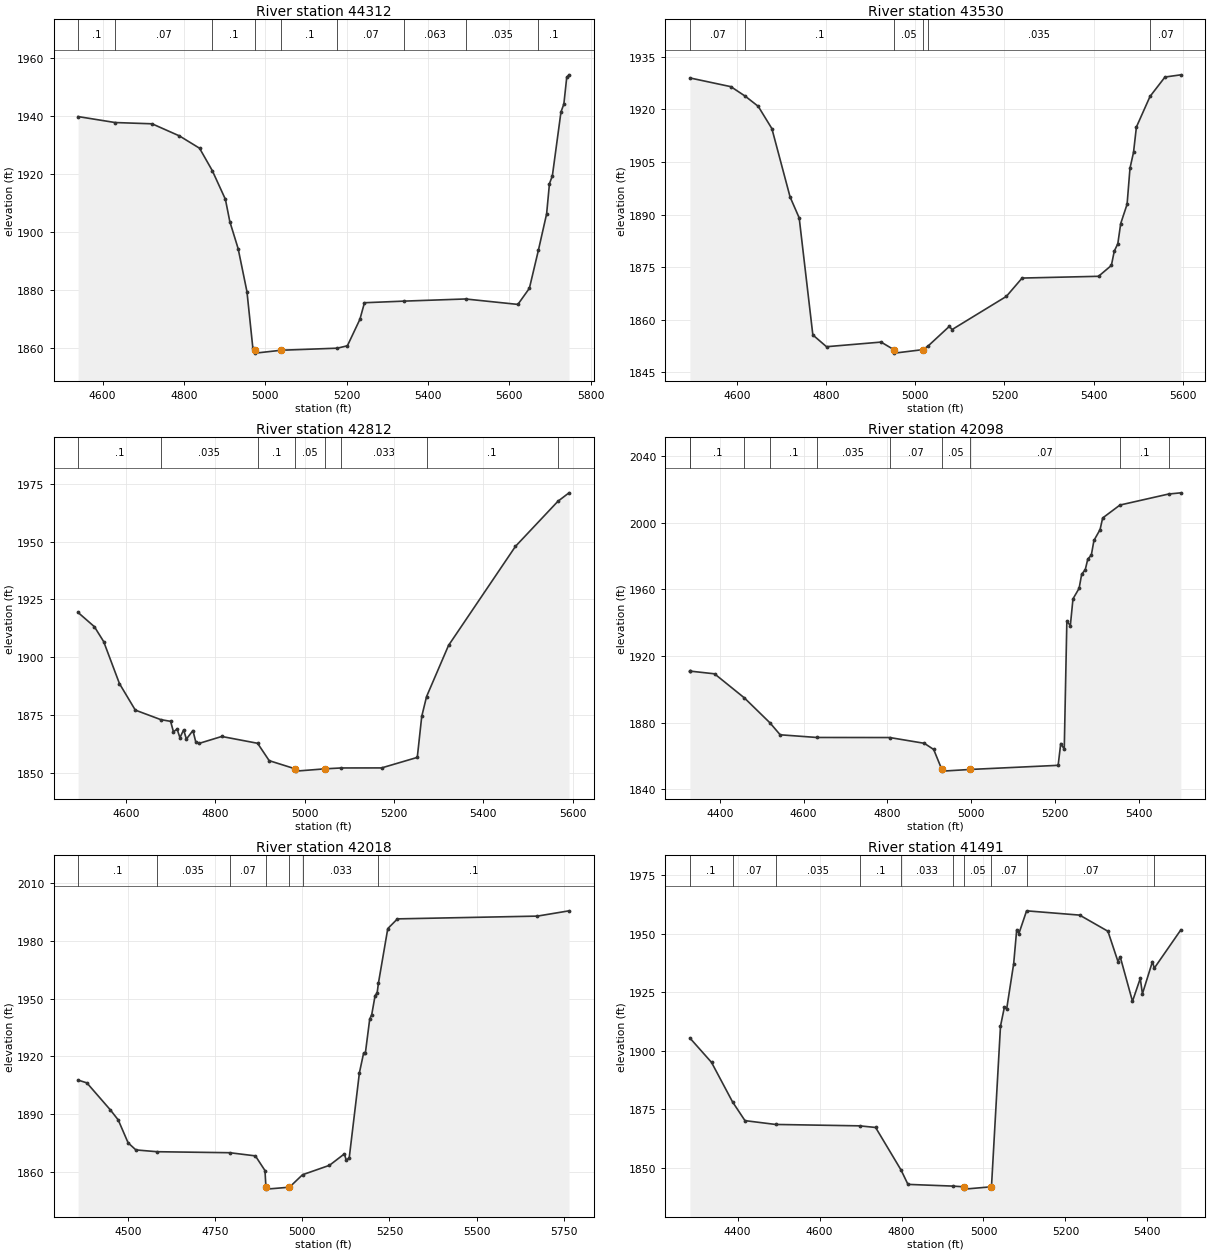
Type RM Length L Ch R = 1 ,44312   ,782,782,782
BEGIN DESCRIPTION:
South Fork Guadalupe River 81.1
END DESCRIPTION:
XS GIS Cut Line= 4
      1846282.08     13912146.84      1846138.87     13911739.33
      1845994.34     13911504.96      1845638.77     13911153.28
#Sta/Elev= 30
  4539.6 1939.86  4630.6  1937.8  4721.6 1937.36  4788.9 1933.17  4838.3 1928.92
  4869.6 1921.19  4901.9 1911.26  4912.8 1903.54  4933.2 1894.23  4954.9 1879.35
  4969.5  1859.7    4974 1859.09  4975.5 1858.09  5039.4 1859.09  5176.9  1859.8
  5201.9 1860.62  5232.7 1869.78  5243.9 1875.51  5340.2 1876.06  5492.4 1876.81
  5621.2 1874.93  5649.5  1880.5  5671.7 1893.67  5691.9 1906.23  5698.9 1916.69
    5706 1919.35  5727.2 1941.45  5734.3  1944.2  5741.4 1953.46    5747 1954.29
#Mann= 9 ,-1 , 0
  4539.6      .1       0  4630.6     .07       0  4869.6      .1       0
    4974     .05       0  5039.4      .1       0  5176.9     .07       0
  5340.2    .063       0  5492.4    .035       0  5671.7      .1       0
Bank Sta=4974,5039.4
XS Rating Curve= 0 ,0
Exp/Cntr=0.3,0.1

Type RM Length L Ch R = 1 ,43530   ,718,718,718
BEGIN DESCRIPTION:
South Fork Guadalupe River 61.0
END DESCRIPTION:
XS GIS Cut Line= 3
      1846474.99     13911775.03        1846575.       13911275.
      1846114.97     13910905.47
#Sta/Elev= 30
  4495.2 1928.97    4587 1926.48    4619 1923.78  4648.2 1920.88  4678.8 1914.53
  4719.6 1895.03    4740 1889.06  4770.6 1855.68  4801.2 1852.32  4923.5 1853.64
    4952 1851.49  4953.5 1850.49  5017.4 1851.49  5029.7 1852.62  5076.3 1858.11
  5082.7 1857.22  5204.3 1866.68  5239.5  1871.9  5410.7  1872.4  5439.5  1875.5
    5446 1879.59  5453.9 1881.67  5460.4 1887.44  5474.7 1892.95  5481.2 1903.23
  5489.1 1907.74  5495.6 1914.98  5526.1  1923.7  5559.6 1929.23  5595.2 1929.86
#Mann= 6 ,-1 , 0
  4495.2     .07       0    4619      .1       0    4952     .05       0
  5017.4      .1       0  5029.7    .035       0  5526.1     .07       0
Bank Sta=4952,5017.4
XS Rating Curve= 0 ,0
Exp/Cntr=0.3,0.1

Type RM Length L Ch R = 1 ,42812   ,714,714,714
BEGIN DESCRIPTION:
South Fork Guadalupe River 60.0
END DESCRIPTION:
XS GIS Cut Line= 3
      1846824.98     13911575.02        1847225.       13911275.
        1847225.     13910675.03
#Sta/Elev= 30
  4492.2  1919.3  4528.7 1913.16  4549.5 1906.71  4584.9 1888.51  4620.4 1877.05
  4677.5 1872.93  4699.5 1872.19  4705.8  1867.7  4714.1 1868.81  4720.4 1865.11
  4728.7 1868.49  4734.9  1864.5  4749.5 1868.22  4755.8 1863.34  4764.1 1862.69
  4814.1 1865.64  4894.4 1862.69  4920.4 1855.17  4978.5 1851.64    4980 1850.64
  5045.9 1851.64  5081.5 1852.01  5172.2 1852.03  5252.2 1856.58  5262.2 1874.34
    5273  1882.9  5322.2 1905.04  5472.2 1947.92  5567.3 1967.43  5592.2 1971.09
#Mann= 8 ,-1 , 0
  4492.2      .1       0  4677.5    .035       0  4894.4      .1       0
  4978.5     .05       0  5045.9      .1       0  5081.5    .033       0
    5273      .1       0  5567.3     .07       0
Bank Sta=4978.5,5045.9
XS Rating Curve= 0 ,0
Exp/Cntr=0.3,0.1

Type RM Length L Ch R = 1 ,42098   ,80,80,80
BEGIN DESCRIPTION:
South Fork Guadalupe River 59.0
END DESCRIPTION:
XS GIS Cut Line= 3
      1847075.04     13912024.98        1847675.       13911725.
      1847975.01     13911324.98
#Sta/Elev= 30
    4329 1910.87  4330.3 1910.87  4387.7 1909.27    4459 1894.79  4519.7 1879.92
  4544.2 1872.71  4631.7  1871.1  4805.6 1871.06    4888  1867.6  4910.3  1863.9
  4929.7 1851.92  4931.2 1850.92  4997.2 1851.92  5207.1  1854.4  5213.3 1867.47
  5221.7  1864.1  5227.9 1940.91  5236.2 1938.15  5242.5 1954.22  5257.1 1960.52
  5263.3 1969.06  5271.7 1971.65  5277.9 1978.13  5286.2  1980.4  5292.5 1989.24
  5307.1 1995.76  5313.3 2002.72  5354.5 2010.47  5470.6 2017.08  5499.8  2017.8
#Mann= 10 ,-1 , 0
    4329     .07       0  4330.3      .1       0    4459     .07       0
  4519.7      .1       0  4631.7    .035       0  4805.6     .07       0
  4929.7     .05       0  4997.2     .07       0  5354.5      .1       0
  5470.6     .07       0
Bank Sta=4929.7,4997.2
XS Rating Curve= 0 ,0
Exp/Cntr=0.3,0.1

Type RM Length L Ch R = 1 ,42018   ,527,527,527
BEGIN DESCRIPTION:
South Fork Guadalupe River 59.1
END DESCRIPTION:
XS GIS Cut Line= 4
      1847142.55     13912055.58      1847619.51     13911811.21
      1847899.89     13911746.97      1848399.07      13911443.6
#Sta/Elev= 30
  4357.2 1907.76  4382.4 1906.31  4449.8 1892.29  4472.3 1887.11  4500.7 1875.22
  4522.9 1871.57  4583.5 1870.64  4792.1 1870.12  4865.6 1868.48  4893.1 1860.87
  4895.8 1852.25  4897.3 1851.25  4963.3 1852.25  5000.7  1858.7    5078 1863.59
  5120.9 1869.54    5126 1866.22  5134.7 1867.53  5163.8 1911.51  5175.7 1921.57
  5180.8 1921.57  5193.4 1939.36  5199.2 1941.71  5208.9 1951.59  5214.7 1952.93
  5218.5 1958.12  5245.2 1986.27  5272.9 1991.31    5674 1992.74  5764.9 1995.48
#Mann= 7 ,-1 , 0
  4357.2      .1       0  4583.5    .035       0  4792.1     .07       0
  4895.8     .05       0  4963.3     .07       0  5000.7    .033       0
  5218.5      .1       0
Bank Sta=4895.8,4963.3
XS Rating Curve= 0 ,0
Exp/Cntr=0.3,0.1

Type RM Length L Ch R = 1 ,41491   ,791,791,791
BEGIN DESCRIPTION:
South Fork Guadalupe River 58.0
END DESCRIPTION:
XS GIS Cut Line= 3
      1847223.36     13912348.91      1847939.24     13912204.82
      1848375.04     13912375.02
#Sta/Elev= 30
  4283.6 1905.34  4336.3 1894.95  4387.5  1878.1  4417.9 1870.06  4492.5 1868.43
  4697.8 1867.83  4736.7 1867.14  4798.7 1848.99  4815.7 1842.82  4924.4 1842.09
    4952 1841.79  4953.5 1840.79  5019.5 1841.79  5041.5 1910.42  5051.2 1918.71
  5056.6 1917.81  5073.7 1937.14  5081.1 1951.68  5086.4 1949.99  5105.2 1959.71
  5234.7 1957.88  5303.7 1950.98  5328.2 1938.04  5333.6 1940.11  5363.6 1921.05
  5382.6  1930.8  5387.9 1924.27  5412.4 1938.02  5416.8  1935.2  5481.7 1951.59
#Mann= 10 ,-1 , 0
  4283.6      .1       0  4387.5     .07       0  4492.5    .035       0
  4697.8      .1       0  4798.7    .033       0  4924.4     .07       0
    4952     .05       0  5019.5     .07       0  5105.2     .07       0
  5416.8      .1       0
Bank Sta=4952,5019.5
XS Rating Curve= 0 ,0
Exp/Cntr=0.3,0.1

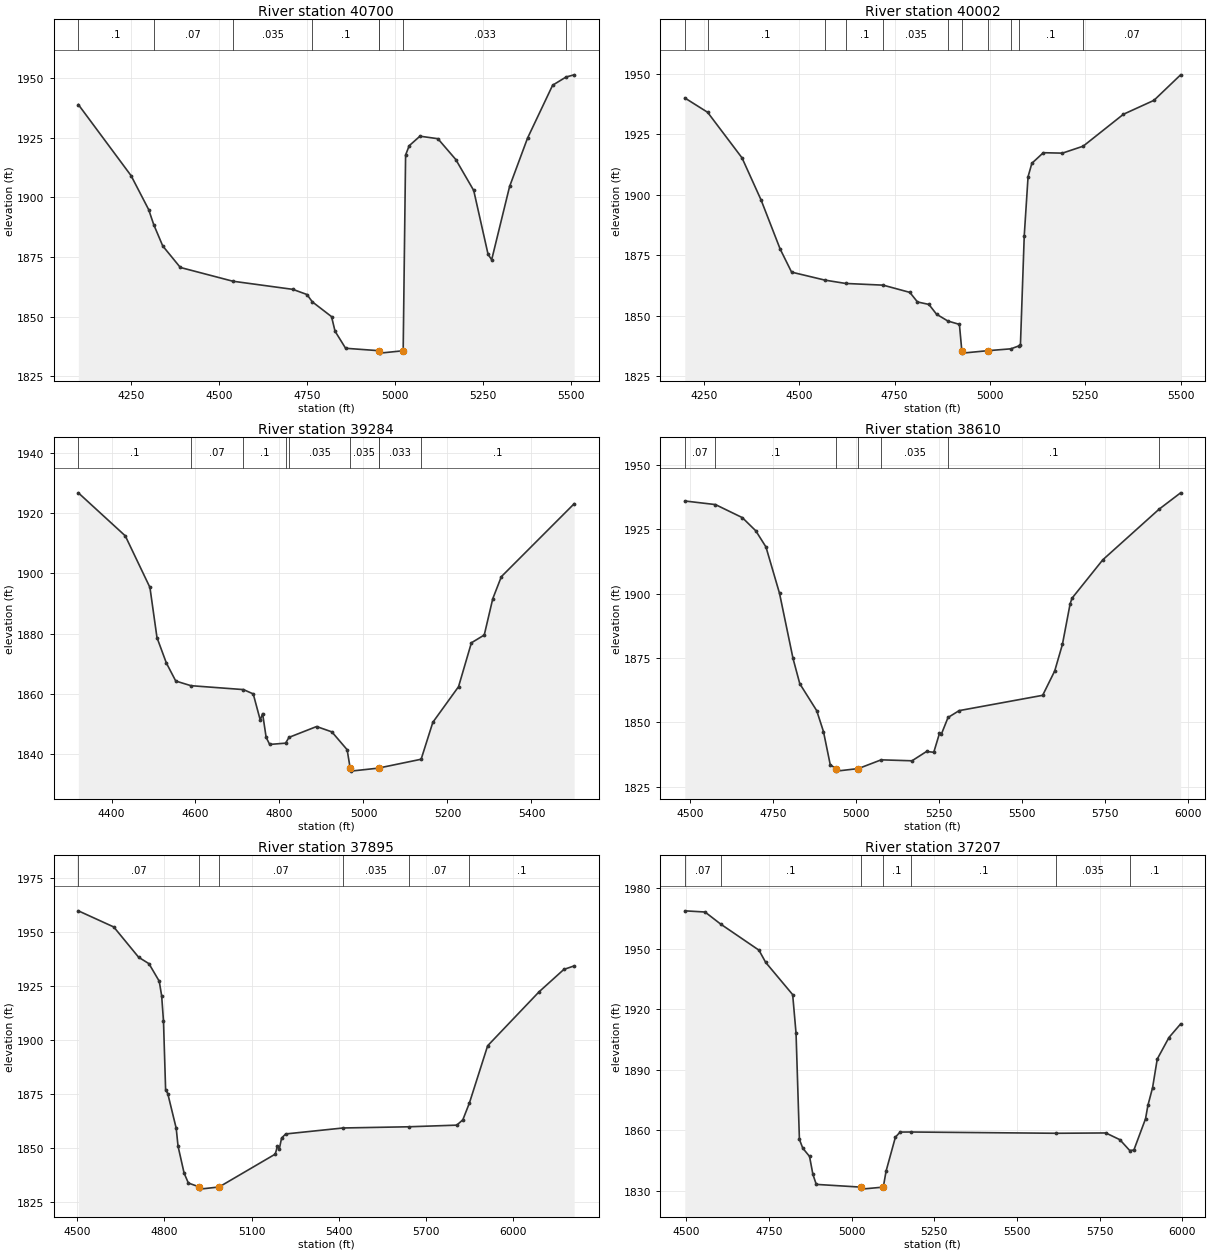
Type RM Length L Ch R = 1 ,40700   ,698,698,698
BEGIN DESCRIPTION:
South Fork Guadalupe River 57.0
END DESCRIPTION:
XS GIS Cut Line= 3
      1847075.02       13912825.        1847975.       13912825.
      1848475.02       13912925.
#Sta/Elev= 30
  4099.1 1939.02  4249.1 1909.15  4299.1  1894.9  4313.5 1888.59  4339.1 1879.64
  4389.1  1870.6  4538.5 1864.82  4709.1  1861.4  4749.1 1859.24  4764.6 1856.14
  4819.1 1849.95  4829.1 1843.82  4859.1 1836.66  4954.6 1835.63  4955.3 1835.62
  4956.8 1834.62  5022.8 1835.62  5029.7 1917.83  5039.9 1921.72  5070.5 1925.73
  5121.5 1924.67  5172.4 1915.93  5223.4 1902.93  5264.2 1876.13  5274.4 1873.81
  5325.4  1904.6  5376.4  1924.9  5447.8 1947.14  5486.2  1950.6    5509  1951.5
#Mann= 8 ,-1 , 0
  4099.1      .1       0  4313.5     .07       0  4538.5    .035       0
  4764.6      .1       0  4954.6    .033       0  4955.3     .05       0
  5022.8    .033       0  5486.2     .07       0
Bank Sta=4955.3,5022.8
XS Rating Curve= 0 ,0
Exp/Cntr=0.3,0.1

Type RM Length L Ch R = 1 ,40002   ,718,718,718
BEGIN DESCRIPTION:
South Fork Guadalupe River 56.0
END DESCRIPTION:
XS GIS Cut Line= 3
      1847074.98       13913325.        1847875.       13913325.
      1848374.98       13913325.
#Sta/Elev= 30
    4200  1940.1  4259.8 1934.17    4350 1915.32    4400  1897.9    4450 1877.61
    4480 1868.06  4567.3 1864.76  4621.6 1863.38  4720.2 1862.67    4790 1859.68
    4810 1855.73    4840  1854.7    4860 1850.66  4889.8 1847.83    4920 1846.45
  4926.3 1835.56  4927.8 1834.56  4993.8 1835.56    5055 1836.34  5076.6 1837.59
    5080 1837.93    5090 1883.12    5100 1907.52    5110 1913.07    5140 1917.45
    5190 1917.27  5244.5 1920.15    5350 1933.35    5430  1939.1    5500 1949.66
#Mann= 11 ,-1 , 0
    4200     .07       0  4259.8      .1       0  4567.3     .07       0
  4621.6      .1       0  4720.2    .035       0  4889.8      .1       0
  4926.3     .05       0  4993.8      .1       0    5055    .033       0
  5076.6      .1       0  5244.5     .07       0
Bank Sta=4926.3,4993.8
XS Rating Curve= 0 ,0
Exp/Cntr=0.3,0.1

Type RM Length L Ch R = 1 ,39284   ,674,674,674
BEGIN DESCRIPTION:
South Fork Guadalupe River 55.0
END DESCRIPTION:
XS GIS Cut Line= 3
      1847125.01       13913625.        1847725.       13913925.
      1848224.99       13913825.
#Sta/Elev= 30
    4321 1926.71  4432.8 1912.44  4491.5 1895.33  4508.3 1878.69  4530.6 1870.28
    4553 1864.29  4589.1 1862.75  4714.3 1861.45  4737.5 1860.02  4754.2 1851.34
  4759.8  1853.5  4768.2 1845.63  4776.6 1843.26  4814.5 1843.69  4822.7 1845.61
  4888.4  1849.2  4924.7 1847.43  4961.1 1841.51  4968.3 1835.41  4969.8 1834.41
  5035.8 1835.41  5036.1 1835.43  5137.3 1838.35  5165.2 1850.61  5226.4 1862.42
    5257 1876.97  5287.6 1879.55  5307.9  1891.6  5328.3  1898.9  5501.7 1923.09
#Mann= 9 ,-1 , 0
    4321      .1       0  4589.1     .07       0  4714.3      .1       0
  4814.5     .07       0  4822.7    .035       0  4968.3    .035       0
  5035.8    .035       0  5036.1    .033       0  5137.3      .1       0
Bank Sta=4968.3,5035.8
XS Rating Curve= 0 ,0
Exp/Cntr=0.3,0.1

Type RM Length L Ch R = 1 ,38610   ,715,715,715
BEGIN DESCRIPTION:
South Fork Guadalupe River 54.0
END DESCRIPTION:
XS GIS Cut Line= 3
      1847025.01       13914575.        1847525.       13914475.
      1848425.02     13914074.99
#Sta/Elev= 30
  4483.6 1936.03    4576 1934.63    4657 1929.56  4697.7 1924.42  4728.3 1918.14
  4769.1 1900.15  4809.9 1874.78  4830.3 1864.96  4881.3 1854.49  4901.7 1846.35
  4922.1 1833.47  4939.1 1831.98  4940.6 1830.98    5007 1831.98  5075.6 1835.37
  5168.6    1835  5212.4 1838.62  5234.2 1838.31  5251.3 1845.62  5256.8 1845.26
  5277.2 1851.84  5310.8 1854.51  5562.5 1860.46  5598.8 1869.93    5622 1880.24
  5645.3 1896.05  5650.8 1898.19  5743.8 1913.16  5913.4 1932.83  5978.4  1939.2
#Mann= 7 ,-1 , 0
  4483.6     .07       0    4576      .1       0  4939.1     .05       0
    5007      .1       0  5075.6    .035       0  5277.2      .1       0
  5913.4     .07       0
Bank Sta=4939.1,5007
XS Rating Curve= 0 ,0
Exp/Cntr=0.3,0.1

Type RM Length L Ch R = 1 ,37895   ,688,688,688
BEGIN DESCRIPTION:
South Fork Guadalupe River 53.0
END DESCRIPTION:
XS GIS Cut Line= 3
      1847325.02     13915474.97        1847625.       13915075.
      1848524.99     13914275.01
#Sta/Elev= 30
  4504.8 1959.72  4626.6 1952.26  4712.1 1938.26  4747.5  1935.3  4782.9 1927.19
  4791.2 1920.42  4797.5 1908.72  4804.8 1876.95  4812.1  1875.3  4841.2 1859.22
  4847.5 1850.95  4868.3 1838.54  4882.9 1833.93  4920.8 1832.11  4922.3 1831.11
  4988.7 1832.11  5181.6 1847.29  5189.1 1850.92  5195.8 1849.81  5203.4 1854.73
  5217.6 1856.61  5414.8 1859.37  5639.9 1859.92  5805.4 1860.68  5826.3 1863.14
  5849.1    1871  5911.6 1897.37  6088.5 1922.32  6173.4 1932.63  6208.9 1934.27
#Mann= 6 ,-1 , 0
  4504.8     .07       0  4920.8     .05       0  4988.7     .07       0
  5414.8    .035       0  5639.9     .07       0  5849.1      .1       0
Bank Sta=4920.8,4988.7
XS Rating Curve= 0 ,0
Exp/Cntr=0.3,0.1

Type RM Length L Ch R = 1 ,37207   ,715,715,715
BEGIN DESCRIPTION:
South Fork Guadalupe River 52.0
END DESCRIPTION:
XS GIS Cut Line= 3
      1847475.04     13915674.99        1847975.       13915575.
      1848674.99     13914875.01
#Sta/Elev= 30
  4495.5 1968.77  4556.7 1968.18  4603.7 1962.23  4719.8 1949.25  4740.2 1943.18
  4821.8 1927.19    4832 1908.04  4842.2 1855.35  4852.4 1851.02  4872.8 1846.93
    4883 1838.02  4893.2 1833.05    5028  1831.7  5029.5  1830.7  5095.9  1831.7
  5104.4 1839.67  5132.6  1856.5  5146.8 1859.01  5179.1 1859.04  5619.6 1858.41
    5769 1858.57  5811.5 1855.23  5841.3 1849.86  5853.9 1850.09  5889.2 1865.63
  5896.3 1872.21  5910.5 1881.08  5924.6 1895.23    5960 1905.92  5995.3 1912.66
#Mann= 7 ,-1 , 0
  4495.5     .07       0  4603.7      .1       0    5028     .05       0
  5095.9      .1       0  5179.1      .1       0  5619.6    .035       0
  5841.3      .1       0
Bank Sta=5028,5095.9
XS Rating Curve= 0 ,0
Exp/Cntr=0.3,0.1