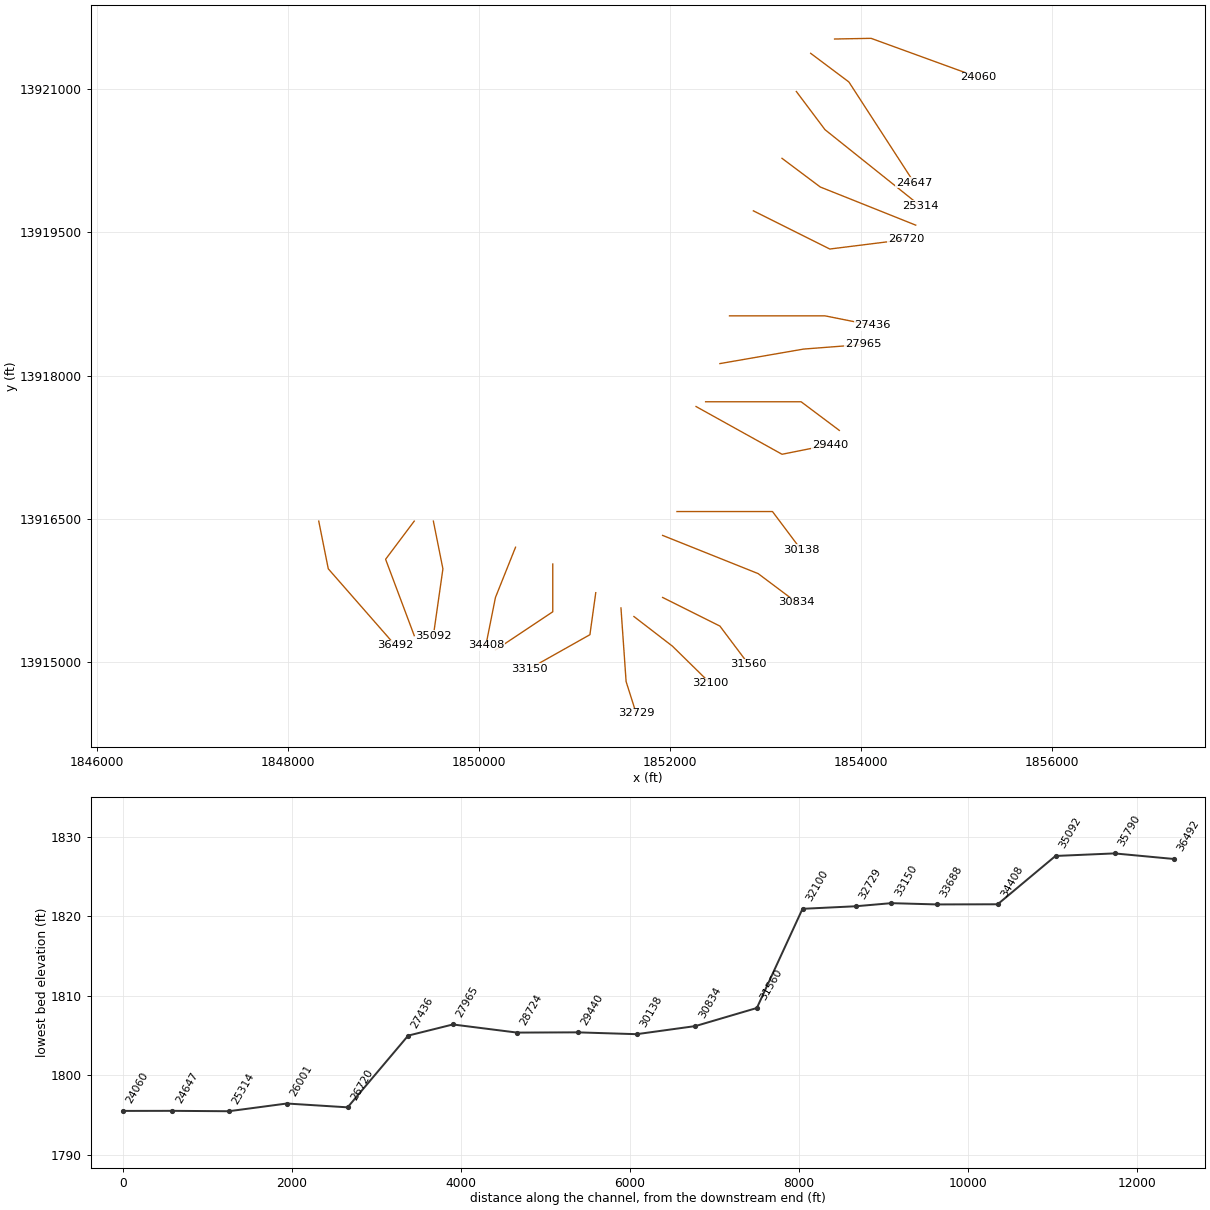
HEC-RAS study South Fork Guadalupe River.prj: South Fork Guadalupe River Base Level Engineering

--- South Fork Guadalupe River.g01 (geometry) --- (continued)

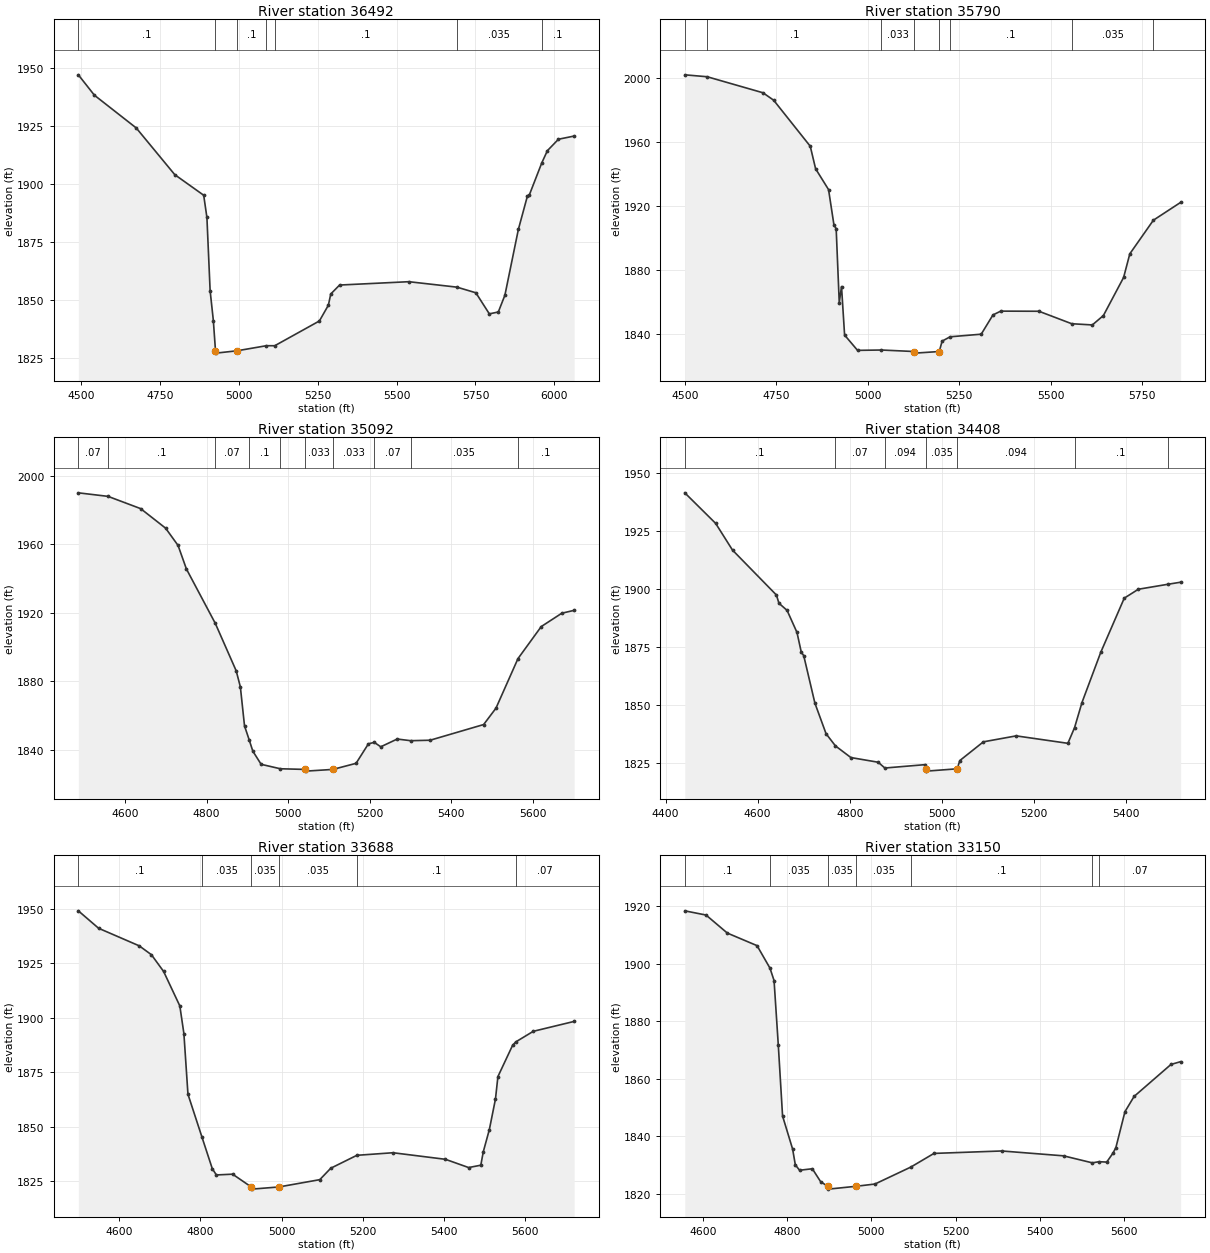
Type RM Length L Ch R = 1 ,36492   ,702,702,702
BEGIN DESCRIPTION:
South Fork Guadalupe River 51.0
END DESCRIPTION:
XS GIS Cut Line= 3
        1848325.     13916475.01        1848425.       13915975.
      1849124.98     13915175.02
#Sta/Elev= 30
  4490.1 1946.87  4541.1  1938.1  4673.7 1924.03    4796 1903.94  4887.8 1895.08
    4898 1885.52  4908.2 1854.01  4918.4 1841.21  4925.2 1828.18  4926.7 1827.18
  4993.3 1828.18  5086.8 1830.37  5113.2 1830.36  5254.8 1841.01  5283.3 1847.79
  5290.9 1852.62  5318.9 1856.46  5538.6  1857.9  5691.4 1855.55  5751.2 1853.13
  5793.9 1844.07  5822.4 1844.87  5843.3 1852.09    5886 1880.37  5914.5 1894.63
  5921.1 1895.32  5960.3    1909  5978.1 1914.25  6013.2 1919.17    6063 1920.54
#Mann= 7 ,-1 , 0
  4490.1      .1       0  4925.2     .05       0  4993.3      .1       0
  5086.8    .033       0  5113.2      .1       0  5691.4    .035       0
  5960.3      .1       0
Bank Sta=4925.2,4993.3
XS Rating Curve= 0 ,0
Exp/Cntr=0.3,0.1

Type RM Length L Ch R = 1 ,35790   ,698,698,698
BEGIN DESCRIPTION:
South Fork Guadalupe River 50.0
END DESCRIPTION:
XS GIS Cut Line= 3
        1849325.       13916475.        1849025.       13916075.
        1849325.       13915275.
#Sta/Elev= 30
    4500 2002.15  4561.1 2000.95  4713.5 1990.92  4742.7 1986.26  4842.7 1957.43
  4857.3 1943.34  4892.7 1930.27  4907.3 1908.33  4913.5 1905.73  4921.9 1859.55
  4928.1 1869.56  4936.5  1839.2  4971.9 1829.61  5037.1 1829.83    5127 1828.88
  5128.5 1827.88  5195.1 1828.88  5202.9  1835.4  5224.8 1838.11  5309.7 1839.74
  5341.8 1851.81  5363.1 1854.18  5467.3  1854.1  5556.9 1846.29  5613.2 1845.53
  5643.5 1851.43  5698.7 1875.28  5715.6 1890.06    5780 1911.12  5854.4 1922.27
#Mann= 8 ,-1 , 0
    4500     .07       0  4561.1      .1       0  5037.1    .033       0
    5127     .05       0  5195.1    .033       0  5224.8      .1       0
  5556.9    .035       0    5780      .1       0
Bank Sta=5127,5195.1
XS Rating Curve= 0 ,0
Exp/Cntr=0.3,0.1

Type RM Length L Ch R = 1 ,35092   ,684,684,684
BEGIN DESCRIPTION:
South Fork Guadalupe River 49.0
END DESCRIPTION:
XS GIS Cut Line= 3
        1849525.     13916475.02        1849625.       13915975.
        1849525.     13915275.03
#Sta/Elev= 30
  4485.2 1990.19  4558.1 1988.12  4638.2 1980.95  4699.4 1969.54    4730 1959.44
  4750.4 1945.73  4821.4  1913.9  4872.7 1886.16  4882.9  1876.8  4893.1 1853.99
  4904.3 1846.01  4913.5 1839.23  4933.9 1831.54  4981.1 1828.94  5041.9 1828.56
  5043.4 1827.56    5110 1828.56  5166.9 1832.12  5197.2 1843.52  5211.6 1844.37
  5227.5 1841.78  5267.9 1846.31  5301.1 1845.34  5348.7 1845.62    5480 1854.78
  5510.3 1864.35  5564.3 1893.31  5621.4 1912.03  5671.9 1919.84  5702.2 1921.52
#Mann= 10 ,-1 , 0
  4485.2     .07       0  4558.1      .1       0  4821.4     .07       0
  4904.3      .1       0  4981.1    .033       0  5041.9    .033       0
    5110    .033       0  5211.6     .07       0  5301.1    .035       0
  5564.3      .1       0
Bank Sta=5041.9,5110
XS Rating Curve= 0 ,0
Exp/Cntr=0.3,0.1

Type RM Length L Ch R = 1 ,34408   ,720,720,720
BEGIN DESCRIPTION:
South Fork Guadalupe River 48.0
END DESCRIPTION:
XS GIS Cut Line= 3
      1850385.24     13916201.23        1850175.       13915675.
        1850075.     13915174.98
#Sta/Elev= 30
  4441.8 1941.39  4508.8 1928.23  4545.4 1916.72  4640.8 1897.35  4646.2 1893.83
  4663.9 1890.74  4685.4 1881.24  4694.7 1872.75    4700 1871.27  4724.3 1850.78
  4748.5 1837.62  4768.9 1832.36  4802.4 1827.34  4861.7 1825.32  4876.2 1822.83
    4964 1824.29    4965 1822.49  4966.5 1821.49  5033.1 1822.49  5039.1 1826.06
  5090.1 1834.11  5161.4 1836.68  5273.6 1833.47  5288.1 1840.22  5304.2 1851.04
    5345 1872.69    5396 1896.01  5426.6 1899.85  5490.1 1901.97  5518.4 1902.88
#Mann= 7 ,-1 , 0
  4441.8      .1       0  4768.9     .07       0  4876.2    .094       0
    4965    .035       0  5033.1    .094       0  5288.1      .1       0
  5490.1     .07       0
Bank Sta=4965,5033.1
XS Rating Curve= 0 ,0
Exp/Cntr=0.3,0.1

Type RM Length L Ch R = 1 ,33688   ,538,538,538
BEGIN DESCRIPTION:
South Fork Guadalupe River 47.0
END DESCRIPTION:
XS GIS Cut Line= 3
        1850775.     13916025.04        1850775.       13915525.
      1850174.96     13915124.97
#Sta/Elev= 30
  4499.6 1949.04  4549.6 1941.04  4649.6 1932.99  4679.6 1928.92  4709.6 1921.26
  4749.6 1905.44  4759.6 1892.77  4769.6 1864.97  4804.4 1845.14  4829.6 1830.81
  4839.6 1827.97  4879.6 1828.32  4925.5 1822.47    4927 1821.47  4993.7 1822.47
  5094.3 1825.81  5121.3 1831.05  5185.6 1836.97  5274.6 1838.15  5403.8 1835.14
  5460.9 1831.36  5490.9 1832.44  5496.9 1838.54  5511.9 1848.74    5527 1862.78
    5533 1873.05    5569 1887.32  5576.8 1888.93  5620.1 1893.81  5720.8 1898.35
#Mann= 6 ,-1 , 0
  4499.6      .1       0  4804.4    .035       0  4925.5    .035       0
  4993.7    .035       0  5185.6      .1       0  5576.8     .07       0
Bank Sta=4925.5,4993.7
XS Rating Curve= 0 ,0
Exp/Cntr=0.3,0.1

Type RM Length L Ch R = 1 ,33150   ,421,421,421
BEGIN DESCRIPTION:
South Fork Guadalupe River 46.0
END DESCRIPTION:
XS GIS Cut Line= 3
        1851225.     13915725.02      1851163.97     13915285.01
      1850525.03     13914925.02
#Sta/Elev= 30
  4556.8 1918.34  4607.3 1916.87  4657.8 1910.61  4728.4 1906.24  4759.1 1898.42
  4768.8 1894.11  4778.9  1871.6    4789 1847.04  4812.9 1835.53  4819.3 1830.07
  4829.4 1828.19  4859.7 1828.71  4879.6 1824.18  4896.3 1822.63  4897.8 1821.63
  4964.5 1822.63  5008.4  1823.4  5093.7  1829.3  5148.6 1834.04  5309.8 1834.89
  5456.3  1833.2  5524.8 1830.76  5540.3 1831.16  5558.9 1831.03  5573.7 1834.13
  5580.6 1836.05  5602.2 1848.55  5623.9 1853.84  5711.5 1864.96  5734.4 1865.92
#Mann= 7 ,-1 , 0
  4556.8      .1       0  4759.1    .035       0  4896.3    .035       0
  4964.5    .035       0  5093.7      .1       0  5524.8    .035       0
  5540.3     .07       0
Bank Sta=4896.3,4964.5
XS Rating Curve= 0 ,0
Exp/Cntr=0.3,0.1

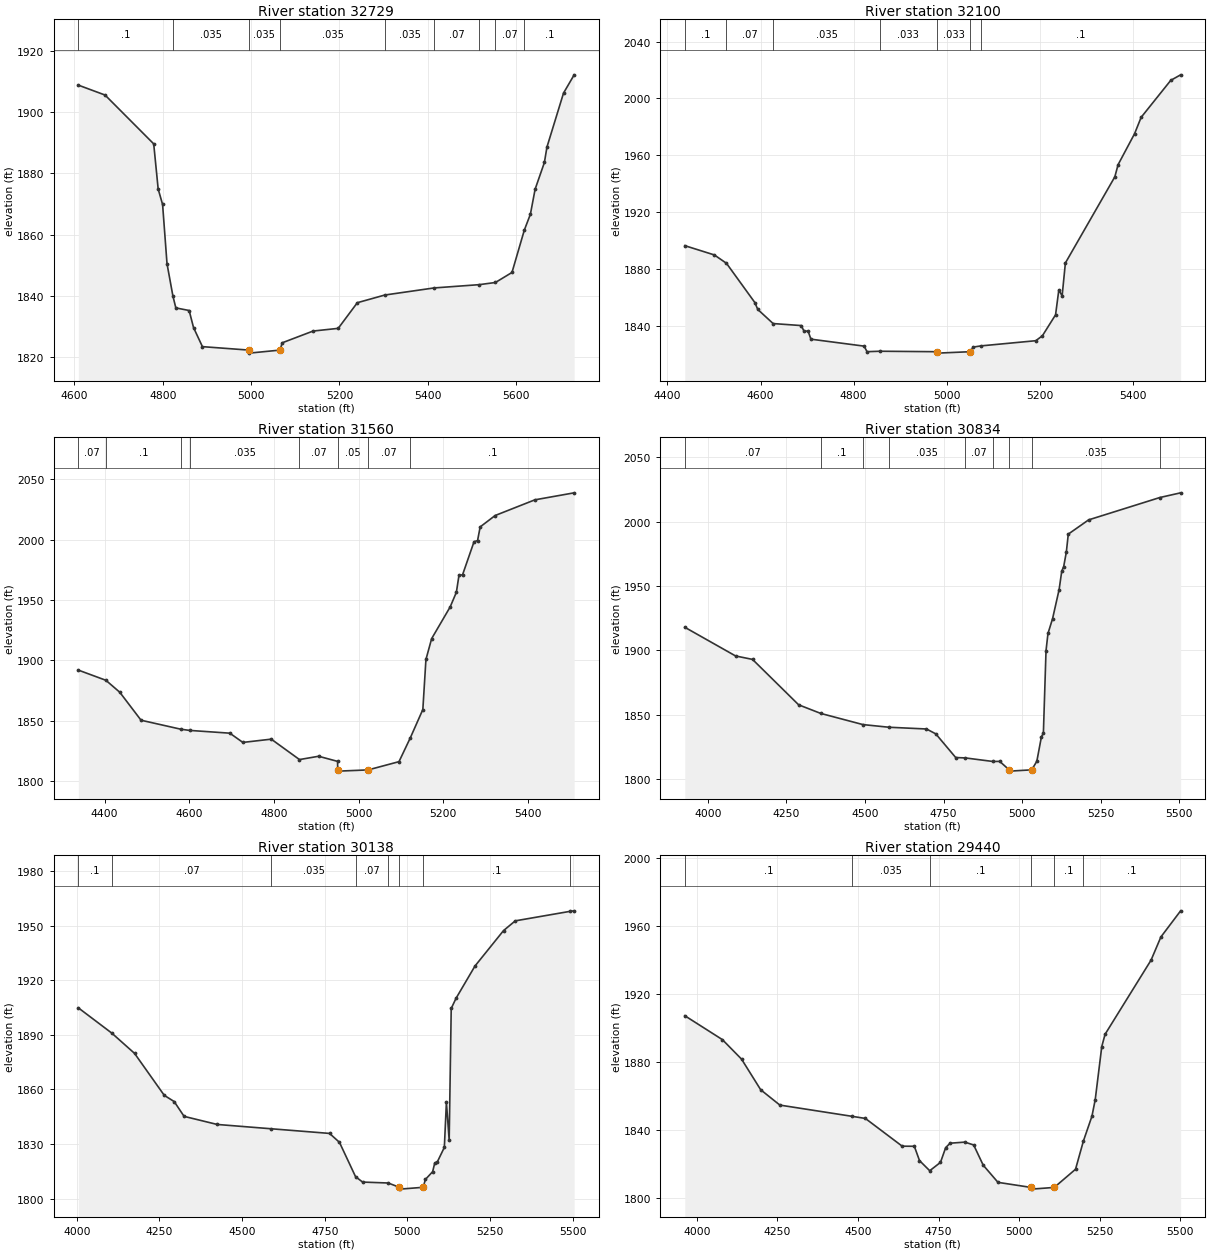
Type RM Length L Ch R = 1 ,32729   ,629,629,629
BEGIN DESCRIPTION:
South Fork Guadalupe River 45.1
END DESCRIPTION:
XS GIS Cut Line= 3
      1851488.93     13915565.31      1851542.73     13914794.01
      1851648.47     13914460.76
#Sta/Elev= 30
  4608.8 1908.88  4669.3 1905.64  4779.5 1889.67  4789.6  1874.9  4799.6 1869.86
  4809.6  1850.5    4823 1839.89  4829.6 1836.03  4859.7 1835.18  4869.7 1829.59
  4889.8 1823.36  4994.2 1822.24  4995.7 1821.24    5066 1822.24  5070.2  1824.6
  5140.4 1828.46  5197.3 1829.34  5240.6 1837.73  5302.8 1840.24  5414.5 1842.56
  5516.6 1843.63  5553.3 1844.34  5590.8 1847.62  5618.8 1861.49  5632.5 1866.66
  5643.2 1874.85  5664.2 1883.58    5670 1888.63  5707.5 1906.27  5731.6 1912.25
#Mann= 9 ,-1 , 0
  4608.8      .1       0    4823    .035       0  4994.2    .035       0
    5066    .035       0  5302.8    .035       0  5414.5     .07       0
  5516.6      .1       0  5553.3     .07       0  5618.8      .1       0
Bank Sta=4994.2,5066
XS Rating Curve= 0 ,0
Exp/Cntr=0.3,0.1

Type RM Length L Ch R = 1 ,32100   ,540,540,540
BEGIN DESCRIPTION:
South Fork Guadalupe River 45.0
END DESCRIPTION:
XS GIS Cut Line= 3
      1851624.98     13915475.01      1852028.04     13915164.59
      1852424.97     13914775.03
#Sta/Elev= 30
  4437.3 1896.49  4500.7 1889.97  4526.8 1884.09  4587.7 1856.51  4594.1 1851.62
    4627 1841.71  4687.4  1840.3  4693.7 1836.14  4701.9 1836.55  4708.2 1830.73
  4822.4 1825.84  4828.7 1821.93  4856.2 1822.25  4978.4 1821.92  4979.9 1820.92
  5050.2 1821.92  5056.7 1825.17  5073.8 1826.02  5191.1 1829.65  5205.3 1833.11
  5233.6 1847.86  5240.6 1865.33  5247.7 1861.18  5254.7 1884.32  5360.9 1944.88
  5367.9 1953.44  5403.3 1975.21  5417.4 1986.72    5481 2012.73  5502.2 2016.61
#Mann= 7 ,-1 , 0
  4437.3      .1       0  4526.8     .07       0    4627    .035       0
  4856.2    .033       0  4978.4    .033       0  5050.2    .033       0
  5073.8      .1       0
Bank Sta=4978.4,5050.2
XS Rating Curve= 0 ,0
Exp/Cntr=0.3,0.1

Type RM Length L Ch R = 1 ,31560   ,726,726,726
BEGIN DESCRIPTION:
South Fork Guadalupe River 44.0
END DESCRIPTION:
XS GIS Cut Line= 3
      1851925.03     13915674.99        1852525.       13915375.
      1852825.01     13914974.99
#Sta/Elev= 30
  4338.1 1892.04  4403.2 1883.61  4435.9 1873.74  4486.2 1850.57  4580.3 1843.12
  4601.2 1842.14  4695.8 1839.86  4726.6 1832.21  4793.7 1834.91  4860.3 1818.02
  4905.5 1820.76  4950.2 1816.53  4950.6 1809.46  4952.1 1808.46  5022.4 1809.46
  5095.3  1816.3  5122.1 1836.06  5151.6 1859.43  5158.9 1900.82  5172.4 1918.09
  5216.2 1944.36  5230.8 1956.45    5237 1970.63  5245.3 1970.82  5272.4 1998.19
  5280.8 1999.21    5287 2010.52  5322.4 2019.94  5416.2 2032.91  5508.9  2038.7
#Mann= 8 ,-1 , 0
  4338.1     .07       0  4403.2      .1       0  4580.3     .07       0
  4601.2    .035       0  4860.3     .07       0  4950.6     .05       0
  5022.4     .07       0  5122.1      .1       0
Bank Sta=4950.6,5022.4
XS Rating Curve= 0 ,0
Exp/Cntr=0.3,0.1

Type RM Length L Ch R = 1 ,30834   ,696,696,696
BEGIN DESCRIPTION:
South Fork Guadalupe River 43.0
END DESCRIPTION:
XS GIS Cut Line= 3
      1851925.04     13916324.99        1852925.       13915925.
        1853325.       13915625.
#Sta/Elev= 30
  3927.1    1918  4088.6 1895.71  4142.5 1893.03  4289.2 1857.73  4359.5 1851.04
  4493.7 1842.36  4576.3  1840.3  4695.8 1838.94  4725.4 1835.15  4788.7 1816.76
  4819.8 1816.44  4906.8  1813.7  4928.7 1813.76  4958.8 1807.19  4960.3 1806.19
  5030.6 1807.19  5046.8  1813.9  5061.4 1832.91  5067.6 1835.62    5076 1899.81
  5082.2 1913.19  5096.8 1924.67  5117.6 1947.26    5126 1961.55  5132.2 1965.21
  5140.6 1976.44  5146.8  1990.4  5211.4 2001.47  5437.9 2018.84  5504.1  2022.5
#Mann= 9 ,-1 , 0
  3927.1     .07       0  4359.5      .1       0  4493.7     .07       0
  4576.3    .035       0  4819.8     .07       0  4906.8    .035       0
  4958.8    .035       0  5030.6    .035       0  5437.9     .07       0
Bank Sta=4958.8,5030.6
XS Rating Curve= 0 ,0
Exp/Cntr=0.3,0.1

Type RM Length L Ch R = 1 ,30138   ,698,698,698
BEGIN DESCRIPTION:
South Fork Guadalupe River 42.0
END DESCRIPTION:
XS GIS Cut Line= 3
      1852075.02       13916575.        1853075.       13916575.
      1853375.01     13916174.98
#Sta/Elev= 30
  4004.6 1904.84  4105.5    1891  4174.6 1879.82  4264.6 1856.73  4294.6 1853.31
  4324.6 1845.17  4424.6 1840.73  4588.5 1838.35  4764.6  1835.8  4794.6 1830.89
  4843.3 1812.01  4864.6 1809.05  4941.9 1808.54    4976 1806.17  4977.5 1805.17
  5047.8 1806.17  5054.6 1810.51  5076.5 1814.76  5082.7 1819.42    5091 1820.28
  5111.9 1828.12  5118.1    1853  5126.5 1832.17  5132.7 1904.49  5147.3 1910.11
  5204.6 1927.84    5291 1947.33  5326.5 1952.67  5491.4 1957.87  5504.6 1958.18
#Mann= 8 ,-1 , 0
  4004.6      .1       0  4105.5     .07       0  4588.5    .035       0
  4843.3     .07       0  4941.9      .1       0    4976     .05       0
  5047.8      .1       0  5491.4     .07       0
Bank Sta=4976,5047.8
XS Rating Curve= 0 ,0
Exp/Cntr=0.3,0.1

Type RM Length L Ch R = 1 ,29440   ,716,716,716
BEGIN DESCRIPTION:
South Fork Guadalupe River 41.0
END DESCRIPTION:
XS GIS Cut Line= 3
      1852274.97     13917675.02        1853175.       13917175.
        1853675.       13917275.
#Sta/Elev= 30
  3962.2 1907.32  4078.9 1893.27  4138.4 1881.81  4197.9 1863.79  4257.4 1854.79
  4482.2 1848.17  4522.8 1846.95  4637.2 1830.64  4674.9 1830.59  4690.9 1822.18
  4722.7 1816.21  4756.1 1821.13  4772.2 1829.79  4785.9 1832.39  4831.6 1833.03
  4859.1 1831.36  4888.8 1819.46  4934.6 1809.38  5037.4  1806.4  5038.9  1805.4
  5109.3  1806.4  5175.4 1817.08  5199.8 1833.65  5226.4 1848.28  5236.6 1858.07
  5256.9 1889.21  5267.1 1896.41  5409.9 1939.99  5440.5 1953.63  5501.7 1968.97
#Mann= 6 ,-1 , 0
  3962.2      .1       0  4482.2    .035       0  4722.7      .1       0
  5037.4     .05       0  5109.3      .1       0  5199.8      .1       0
Bank Sta=5037.4,5109.3
XS Rating Curve= 0 ,0
Exp/Cntr=0.3,0.1

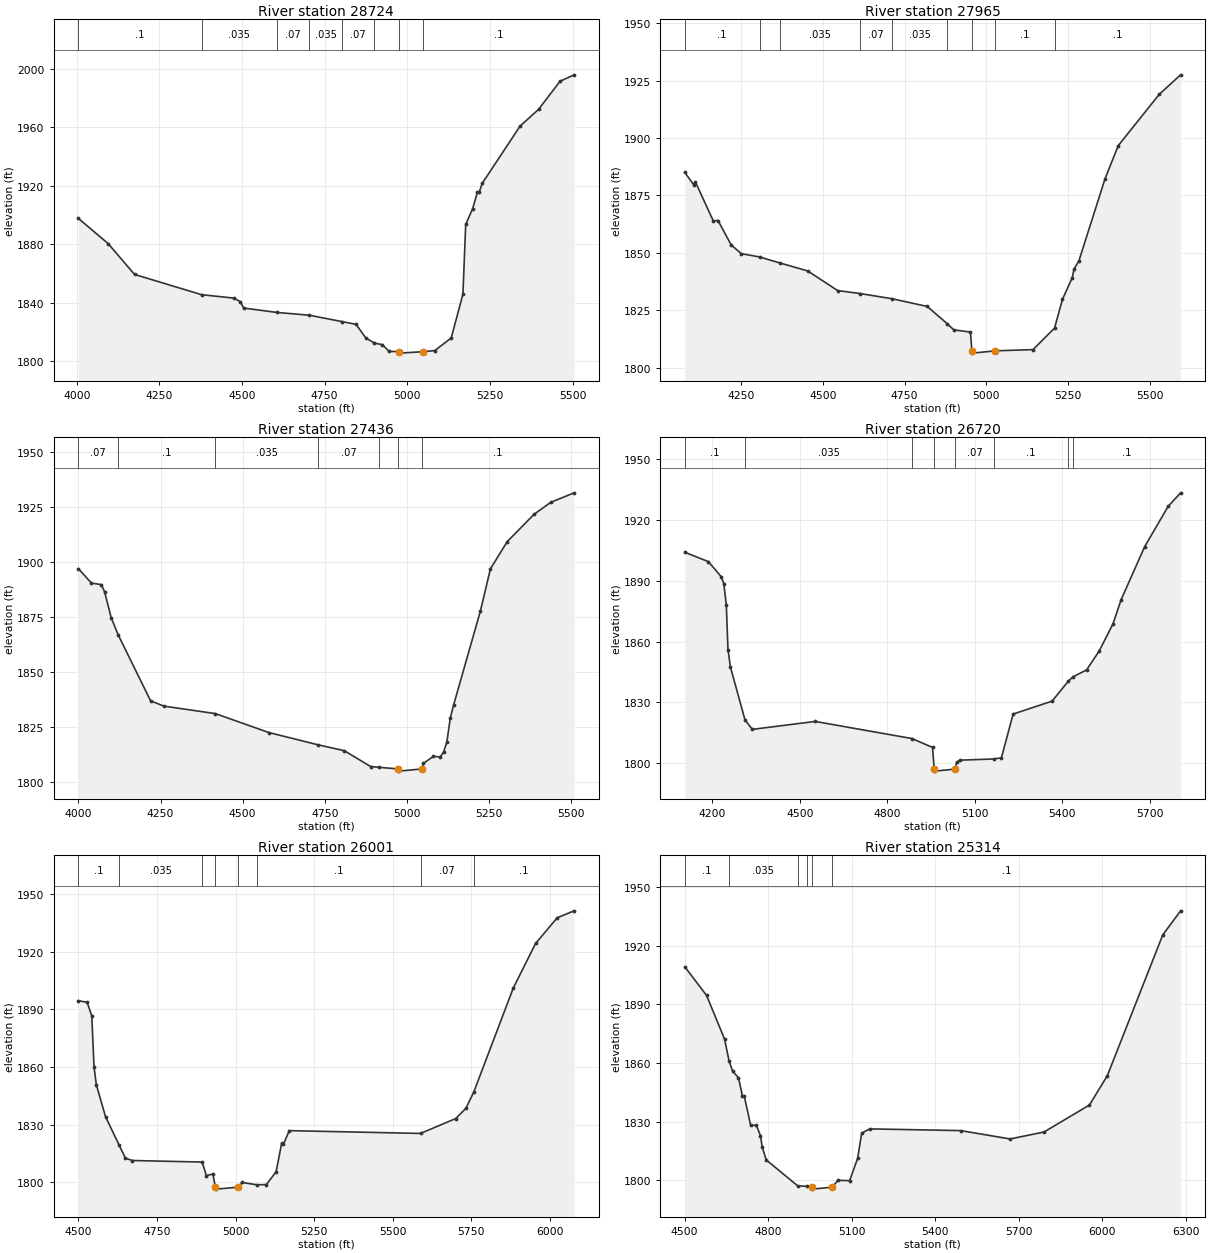
Type RM Length L Ch R = 1 ,28724   ,759,759,759
BEGIN DESCRIPTION:
South Fork Guadalupe River 40.0
END DESCRIPTION:
XS GIS Cut Line= 3
      1852375.02       13917725.        1853375.       13917725.
      1853775.02     13917424.99
#Sta/Elev= 30
  4004.8 1897.69  4094.8 1880.45  4174.8 1859.29  4377.6 1845.41  4474.8 1843.08
  4494.8 1840.65  4504.8 1836.26  4604.9 1833.26  4703.5 1831.34  4802.1 1826.99
  4844.8  1825.1  4874.8 1815.69  4900.7 1812.24  4924.8 1811.16  4944.8 1806.59
    4976 1806.37  4977.5 1805.37  5048.1 1806.37  5082.9 1807.09  5132.9 1815.74
  5168.3 1845.79  5176.7 1893.53  5197.5 1904.18  5212.1 1915.59  5218.3 1916.09
  5226.7 1921.68  5341.2  1960.9  5397.5 1972.45  5462.1 1991.62  5504.8 1996.03
#Mann= 8 ,-1 , 0
  4004.8      .1       0  4377.6    .035       0  4604.9     .07       0
  4703.5    .035       0  4802.1     .07       0  4900.7      .1       0
    4976     .05       0  5048.1      .1       0
Bank Sta=4976,5048.1
XS Rating Curve= 0 ,0
Exp/Cntr=0.3,0.1

Type RM Length L Ch R = 1 ,27965   ,529,529,529
BEGIN DESCRIPTION:
South Fork Guadalupe River 39.0
END DESCRIPTION:
XS GIS Cut Line= 3
      1852525.01       13918125.      1853400.93     13918276.92
      1854024.99       13918325.
#Sta/Elev= 30
  4078.5 1885.03  4105.8 1879.64  4110.9 1880.88  4165.5 1863.93    4180  1864.1
  4220.1  1853.5    4251 1849.67  4307.3 1848.24  4369.3 1845.61  4453.9 1842.16
  4545.4 1833.62  4613.4 1832.33  4712.8 1830.04  4819.4 1826.69  4880.7 1819.14
  4900.6 1816.49  4951.3 1815.56  4955.6 1807.39  4957.1 1806.39  5027.7 1807.39
  5142.4 1807.92  5208.2 1817.28  5232.3 1829.75  5262.4 1839.27  5267.7 1842.96
  5282.5  1846.5  5362.7 1882.37    5403 1896.72  5528.3 1919.04  5593.4 1927.49
#Mann= 9 ,-1 , 0
  4078.5      .1       0  4307.3     .07       0  4369.3    .035       0
  4613.4     .07       0  4712.8    .035       0  4880.7      .1       0
  4955.6     .05       0  5027.7      .1       0  5208.2      .1       0
Bank Sta=4955.6,5027.7
XS Rating Curve= 0 ,0
Exp/Cntr=0.3,0.1

Type RM Length L Ch R = 1 ,27436   ,716,716,716
BEGIN DESCRIPTION:
South Fork Guadalupe River 38.0
END DESCRIPTION:
XS GIS Cut Line= 3
      1852625.04       13918625.        1853625.       13918625.
      1854125.04     13918524.99
#Sta/Elev= 30
  3999.6 1897.09  4039.6 1890.47  4069.6 1889.82  4079.6 1886.51  4099.6 1874.79
  4120.9 1866.96  4219.6 1836.98  4259.6 1834.56  4416.6 1831.16  4579.6 1822.54
    4729 1816.98  4809.6 1814.28  4889.6 1807.09    4915 1806.73  4973.7 1805.99
  4975.2 1804.99  5045.8 1805.99  5050.5 1808.53  5081.1 1811.71  5101.5 1811.43
  5111.7 1813.62  5121.9 1818.28  5132.1 1829.02  5142.3 1835.02  5223.9 1877.75
  5254.5 1896.97  5305.5 1909.31  5387.1 1921.73  5438.1 1927.21  5509.5 1931.54
#Mann= 7 ,-1 , 0
  3999.6     .07       0  4120.9      .1       0  4416.6    .035       0
    4729     .07       0    4915      .1       0  4973.7     .05       0
  5045.8      .1       0
Bank Sta=4973.7,5045.8
XS Rating Curve= 0 ,0
Exp/Cntr=0.3,0.1

Type RM Length L Ch R = 1 ,26720   ,719,719,719
BEGIN DESCRIPTION:
South Fork Guadalupe River 37.0
END DESCRIPTION:
XS GIS Cut Line= 3
      1852875.01     13919724.99        1853675.       13919325.
      1854474.96       13919425.
#Sta/Elev= 30
  4105.5 1904.08  4186.5 1899.44  4231.3 1891.87  4239.6 1888.31    4248 1877.81
  4253.6    1856    4262 1847.41  4312.2 1821.16  4337.5 1816.61  4552.7 1820.52
  4884.5 1812.07  4955.2 1807.69    4961 1796.98  4962.5 1795.98  5033.2 1796.98
  5037.7 1800.36  5050.3  1801.4  5165.3 1801.99  5191.4 1802.57  5231.7 1824.17
  5365.2 1830.55    5421  1840.4  5436.3 1842.49  5483.6 1845.97  5526.5 1855.22
  5574.3 1868.78  5602.1 1880.68  5682.7 1906.81  5763.3 1926.75  5806.1 1933.43
#Mann= 8 ,-1 , 0
  4105.5      .1       0  4312.2    .035       0  4884.5     .07       0
    4961     .05       0  5033.2     .07       0  5165.3      .1       0
    5421     .07       0  5436.3      .1       0
Bank Sta=4961,5033.2
XS Rating Curve= 0 ,0
Exp/Cntr=0.3,0.1

Type RM Length L Ch R = 1 ,26001   ,687,687,687
BEGIN DESCRIPTION:
South Fork Guadalupe River 36.0
END DESCRIPTION:
XS GIS Cut Line= 3
        1853175.       13920275.        1853575.       13919975.
      1854574.96     13919575.01
#Sta/Elev= 30
    4500 1894.48  4528.1 1893.64  4542.7 1886.54    4550 1859.88  4557.3 1850.72
  4586.5 1834.13  4629.4 1819.51    4650 1812.51  4671.9 1811.35  4893.9 1810.54
  4907.3 1803.49  4928.1 1804.33  4935.8 1797.46  4937.3 1796.46    5008 1797.46
  5021.5 1799.92  5067.9 1798.71  5098.3 1798.84  5129.2 1805.55  5146.8 1820.41
  5152.1  1819.7    5171 1826.88  5588.3 1825.43  5700.1 1833.15  5732.4 1838.42
  5757.5 1846.87  5883.2 1900.99  5954.5 1924.29  6023.2 1937.62    6077 1941.22
#Mann= 8 ,-1 , 0
    4500      .1       0  4629.4    .035       0  4893.9     .07       0
  4935.8     .05       0    5008     .07       0  5067.9      .1       0
  5588.3     .07       0  5757.5      .1       0
Bank Sta=4935.8,5008
XS Rating Curve= 0 ,0
Exp/Cntr=0.3,0.1

Type RM Length L Ch R = 1 ,25314   ,667,667,667
BEGIN DESCRIPTION:
South Fork Guadalupe River 35.0
END DESCRIPTION:
XS GIS Cut Line= 3
      1853325.03     13920974.97        1853625.       13920575.
      1854625.01     13919774.99
#Sta/Elev= 30
  4500.6 1909.26  4578.7 1894.64  4643.3 1872.28  4659.4 1861.22  4672.4 1855.86
  4693.3 1852.52  4707.8 1843.02  4714.1 1843.14    4737 1828.24  4757.8 1828.08
  4772.4 1822.86  4778.7  1816.9  4793.3  1810.4  4906.5 1797.12  4941.2 1796.97
  4957.1 1796.49  4958.6 1795.49  5029.4 1796.49    5051    1800  5092.6 1799.82
  5121.4 1811.31  5135.8 1824.12  5164.6 1826.32  5491.2 1825.44  5668.9 1821.17
  5790.5 1824.71  5953.8 1838.54  6017.9 1853.52  6217.2 1925.64  6281.2 1937.91
#Mann= 6 ,-1 , 0
  4500.6      .1       0  4659.4    .035       0  4906.5     .07       0
  4941.2      .1       0  4957.1     .05       0  5029.4      .1       0
Bank Sta=4957.1,5029.4
XS Rating Curve= 0 ,0
Exp/Cntr=0.3,0.1

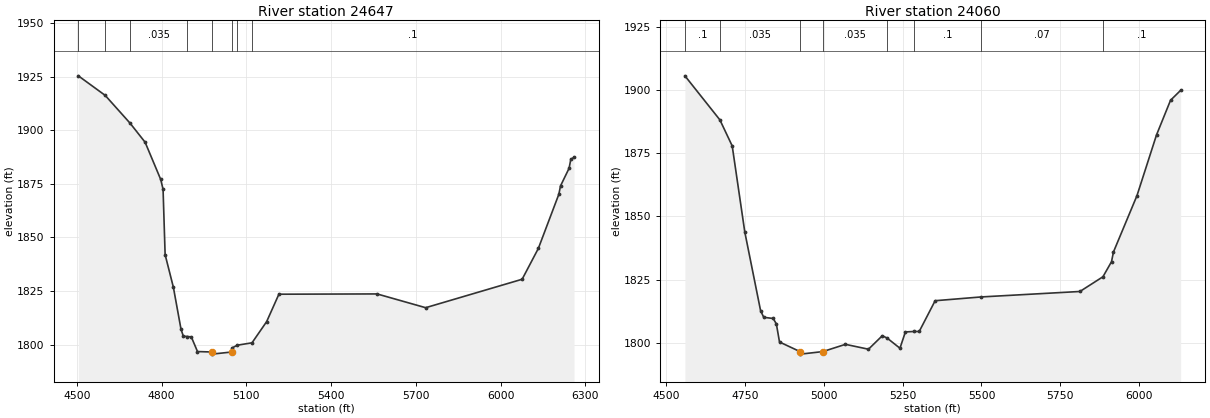
Type RM Length L Ch R = 1 ,24647   ,587,587,587
BEGIN DESCRIPTION:
South Fork Guadalupe River 34.0
END DESCRIPTION:
XS GIS Cut Line= 3
      1853474.97     13921375.02        1853875.       13921075.
      1854557.16     13920021.51
#Sta/Elev= 30
  4505.2 1925.49  4600.3 1916.36  4688.1 1903.42  4741.7 1894.47  4796.9  1877.1
  4805.2 1872.54  4812.5    1842  4841.7 1826.77  4868.8 1807.13  4877.1  1803.9
  4890.7 1803.77  4905.2 1803.58  4927.1 1796.74  4976.7 1796.54  4978.2 1795.54
    5049 1796.54  5049.1 1798.41  5068.4 1799.72  5120.1 1800.82    5172 1810.73
  5215.3 1823.52  5562.8 1823.65  5734.9 1817.22  6076.5  1830.5  6133.9  1844.9
  6206.4 1870.18  6212.4 1874.09  6242.7 1882.33  6248.7 1886.42  6260.3 1887.47
#Mann= 8 ,-1 , 0
  4505.2      .1       0  4600.3     .07       0  4688.1    .035       0
  4890.7      .1       0  4976.7     .05       0    5049      .1       0
  5068.4    .033       0  5120.1      .1       0
Bank Sta=4976.7,5049
XS Rating Curve= 0 ,0
Exp/Cntr=0.3,0.1

Type RM Length L Ch R = 1 ,24060   ,837,837,837
BEGIN DESCRIPTION:
South Fork Guadalupe River 33.0
END DESCRIPTION:
XS GIS Cut Line= 3
      1853725.02       13921525.      1854107.29     13921532.03
      1855225.04     13921124.98
#Sta/Elev= 30
  4559.7 1905.52  4670.7  1888.1  4709.7 1877.82  4749.7 1843.73  4799.7 1812.71
  4809.7 1810.08  4839.7 1809.62  4849.7 1807.47  4859.7 1800.32  4924.7 1796.53
  4926.2 1795.53    4997 1796.53  5068.8  1799.4  5141.8 1797.47  5185.7 1802.81
  5201.2 1801.85  5241.6 1797.86  5258.9  1804.3  5286.7 1804.48  5302.7 1804.48
  5353.2 1816.64    5499 1818.13  5812.3 1820.29  5885.3 1826.11  5912.4 1832.05
  5918.7 1835.93  5993.2 1858.18  6055.1 1882.15  6099.6 1895.86  6131.6 1899.78
#Mann= 8 ,-1 , 0
  4559.7      .1       0  4670.7    .035       0  4924.7     .05       0
    4997    .035       0  5201.2    .035       0  5286.7      .1       0
    5499     .07       0  5885.3      .1       0
Bank Sta=4924.7,4997
XS Rating Curve= 0 ,0
Exp/Cntr=0.3,0.1