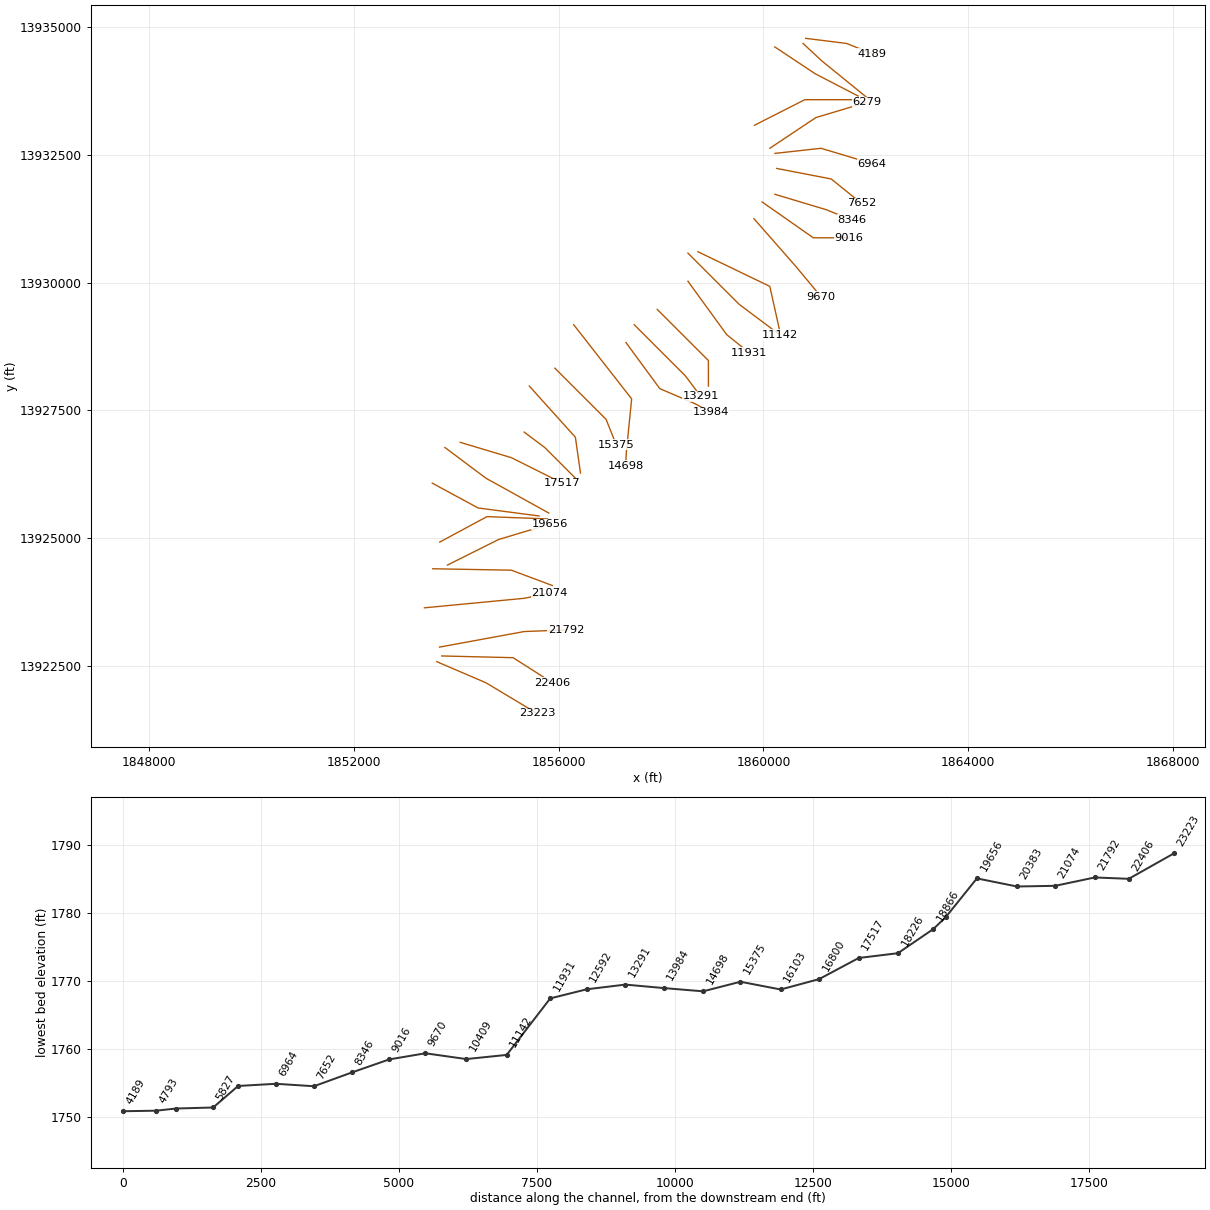
HEC-RAS study South Fork Guadalupe River.prj: South Fork Guadalupe River Base Level Engineering

--- South Fork Guadalupe River.g01 (geometry) --- (continued)

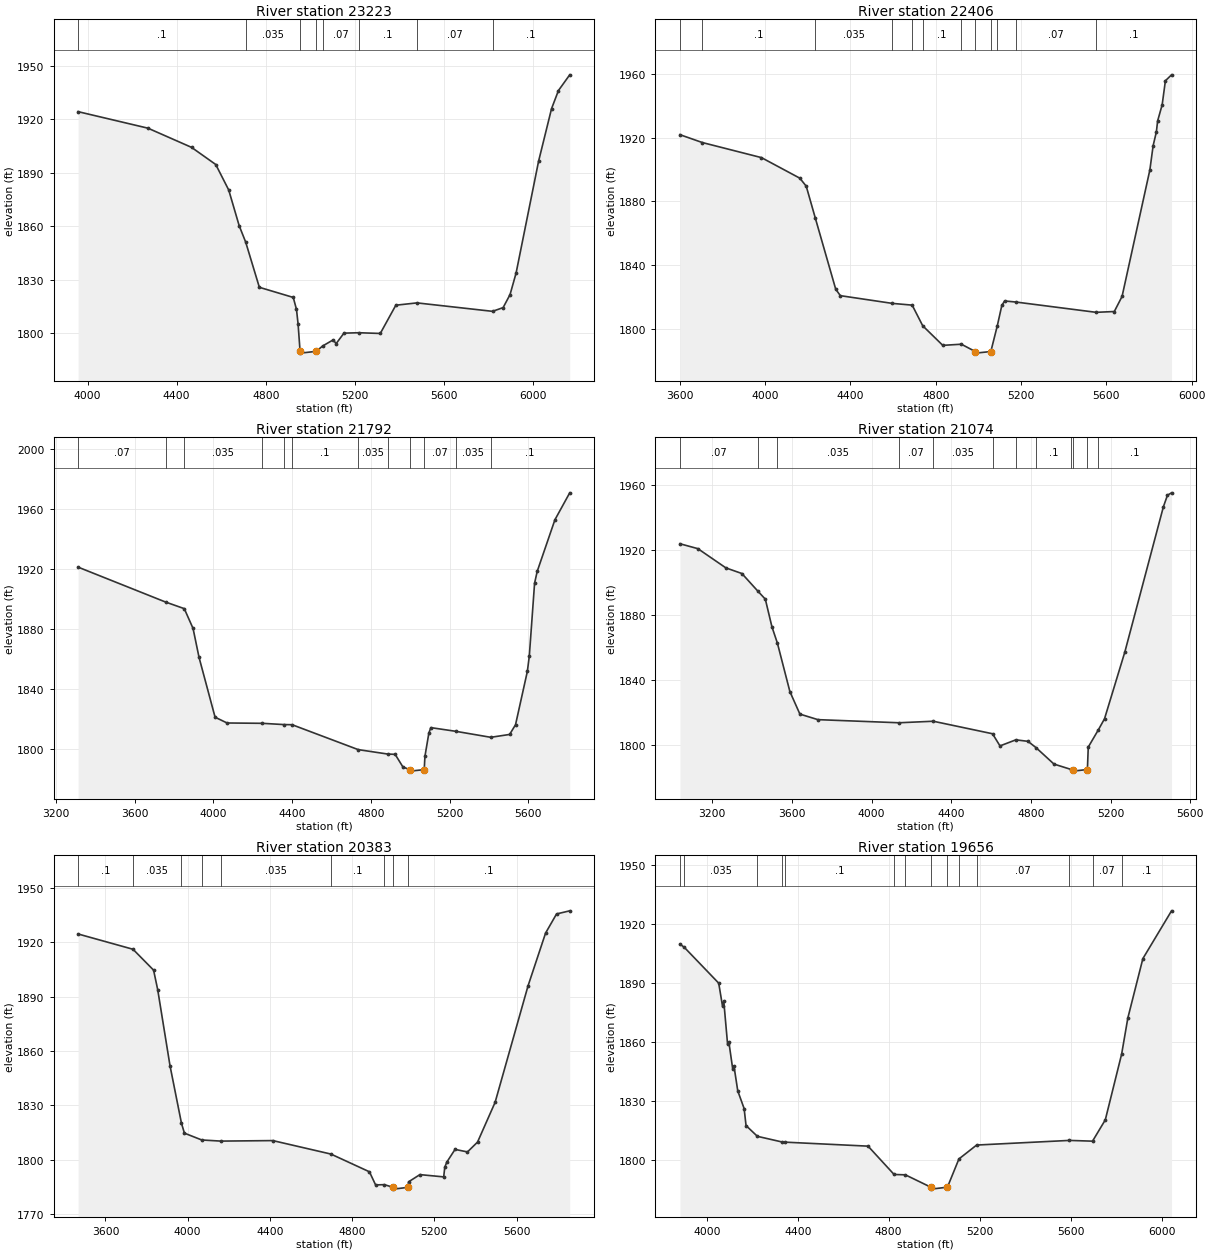
Type RM Length L Ch R = 1 ,23223   ,817,817,817
BEGIN DESCRIPTION:
South Fork Guadalupe River 32.0
END DESCRIPTION:
XS GIS Cut Line= 3
      1853616.57     13922586.13        1854575.       13922175.
      1855575.02     13921574.99
#Sta/Elev= 30
  3957.1 1924.31  4270.9 1915.04  4466.8 1904.27  4575.6 1894.64  4633.8 1880.34
  4680.9 1860.26    4710 1851.11  4771.5 1825.71  4923.8 1820.03  4938.4 1813.29
  4945.6 1805.01  4954.5 1789.76    4956 1788.76  5027.4 1789.76  5055.3 1792.72
    5103 1796.18  5116.6 1794.11  5151.6 1799.98  5218.6 1800.21  5314.9  1799.8
  5384.8 1815.66    5480 1816.96  5819.3 1812.22  5866.9 1814.31    5898 1821.62
  5925.2 1833.73  6026.2 1896.46  6084.5 1925.99  6115.6 1936.19  6166.2 1944.99
#Mann= 8 ,-1 , 0
  3957.1      .1       0    4710    .035       0  4954.5    .035       0
  5027.4    .035       0  5055.3     .07       0  5218.6      .1       0
    5480     .07       0  5819.3      .1       0
Bank Sta=4954.5,5027.4
XS Rating Curve= 0 ,0
Exp/Cntr=0.3,0.1

Type RM Length L Ch R = 1 ,22406   ,614,614,614
BEGIN DESCRIPTION:
South Fork Guadalupe River 31.0
END DESCRIPTION:
XS GIS Cut Line= 3
       1853713.1     13922697.59      1855107.15     13922664.15
      1855875.02     13922174.99
#Sta/Elev= 30
  3600.8 1921.82  3706.1 1916.89  3982.8 1907.47  4162.9 1894.58  4192.9 1889.57
  4234.8 1869.92  4331.2 1825.04  4352.9 1821.01  4596.5 1816.17  4689.6 1815.08
  4739.1 1802.14  4833.1 1789.89  4920.3  1790.6  4985.5 1786.02    4987 1785.02
  5058.4 1786.02  5088.8 1802.17    5110 1814.92  5123.1 1817.69  5175.3 1817.03
  5552.3 1810.57  5637.3 1811.08  5673.7 1820.52  5804.1 1899.79  5819.3 1914.91
  5834.5 1923.55  5840.5 1930.47  5861.7 1940.54  5876.9 1955.61  5905.7 1959.31
#Mann= 12 ,-1 , 0
  3600.8     .07       0  3706.1      .1       0  4234.8    .035       0
  4596.5      .1       0  4689.6     .07       0  4739.1      .1       0
  4920.3     .07       0  4985.5     .05       0  5058.4     .07       0
  5088.8      .1       0  5175.3     .07       0  5552.3      .1       0
Bank Sta=4985.5,5058.4
XS Rating Curve= 0 ,0
Exp/Cntr=0.3,0.1

Type RM Length L Ch R = 1 ,21792   ,718,718,718
BEGIN DESCRIPTION:
South Fork Guadalupe River 30.0
END DESCRIPTION:
XS GIS Cut Line= 3
      1853670.62     13922870.77        1855325.       13923175.
      1856140.16     13923206.92
#Sta/Elev= 30
  3312.8 1921.19  3757.6 1897.91  3852.2 1893.53  3896.8 1880.32  3927.3 1860.99
  4008.7 1821.16  4069.7 1817.31  4248.6 1817.09  4358.5 1816.25    4400 1816.16
  4735.8 1799.56  4884.9 1796.62  4923.7 1796.39  4963.3 1787.96  4998.5 1786.22
    5000 1785.22  5071.4 1786.22    5075 1795.08    5095 1810.61    5105 1814.22
  5231.9 1811.76  5409.5 1807.76  5505.3 1809.67  5535.3 1816.14  5595.4 1851.69
  5605.4 1862.01  5632.1 1910.45  5645.4 1918.35  5735.5 1952.78  5810.7 1970.73
#Mann= 12 ,-1 , 0
  3312.8     .07       0  3757.6      .1       0  3852.2    .035       0
  4248.6      .1       0  4358.5    .035       0    4400      .1       0
  4735.8    .035       0  4884.9     .07       0  4998.5     .05       0
  5071.4     .07       0  5231.9    .035       0  5409.5      .1       0
Bank Sta=4998.5,5071.4
XS Rating Curve= 0 ,0
Exp/Cntr=0.3,0.1

Type RM Length L Ch R = 1 ,21074   ,691,691,691
BEGIN DESCRIPTION:
South Fork Guadalupe River 29.0
END DESCRIPTION:
XS GIS Cut Line= 3
      1853375.39      13923639.1        1855325.       13923825.
      1855825.04     13923925.01
#Sta/Elev= 30
  3037.5 1923.81  3127.5  1920.8  3268.2 1908.97  3348.5 1905.51  3428.3 1894.73
  3466.2 1889.74  3499.2 1872.81    3527 1862.62  3589.6 1832.88  3639.8 1819.06
  3730.2 1815.65  4137.4 1813.73  4309.6 1814.67  4607.1 1806.97  4644.4  1799.5
  4724.2 1803.23    4785 1802.31  4825.3 1798.45  4915.6 1788.32  5001.9    1785
  5010.4 1784.99  5011.9 1783.99  5083.4 1784.99  5087.7 1798.77  5138.4 1809.39
  5169.3 1816.17  5271.3 1857.22  5465.1 1946.62  5485.5 1953.68  5505.9 1955.13
#Mann= 12 ,-1 , 0
  3037.5     .07       0  3428.3      .1       0    3527    .035       0
  4137.4     .07       0  4309.6    .035       0  4607.1      .1       0
  4724.2    .035       0  4825.3      .1       0  5001.9    .035       0
  5010.4     .05       0  5083.4    .035       0  5138.4      .1       0
Bank Sta=5010.4,5083.4
XS Rating Curve= 0 ,0
Exp/Cntr=0.3,0.1

Type RM Length L Ch R = 1 ,20383   ,727,727,727
BEGIN DESCRIPTION:
South Fork Guadalupe River 28.0
END DESCRIPTION:
XS GIS Cut Line= 3
      1853537.93     13924402.83        1855075.       13924375.
      1855874.98     13924075.01
#Sta/Elev= 30
  3467.1 1924.56  3734.2 1916.13  3834.2 1904.63  3854.2 1893.91  3914.2 1851.89
    3970 1820.15  3984.3 1814.75  4068.6 1810.99  4161.3 1810.37  4414.3 1810.65
  4696.8 1803.23  4884.4 1793.44  4914.4  1786.2  4956.6 1786.36  4999.9 1784.89
  5001.4 1783.89  5073.1 1784.89  5074.7 1787.91  5129.9 1791.89  5245.6 1790.64
    5251 1795.98  5260.7 1798.75  5300.8 1805.79  5361.3  1804.4  5410.3 1809.82
  5495.7 1831.72  5655.9 1895.93  5741.3 1925.06  5794.7 1935.61  5858.8 1937.33
#Mann= 9 ,-1 , 0
  3467.1      .1       0  3734.2    .035       0    3970      .1       0
  4068.6     .07       0  4161.3    .035       0  4696.8      .1       0
  4956.6    .033       0  4999.9    .033       0  5073.1      .1       0
Bank Sta=4999.9,5073.1
XS Rating Curve= 0 ,0
Exp/Cntr=0.3,0.1

Type RM Length L Ch R = 1 ,19656   ,563,563,563
BEGIN DESCRIPTION:
South Fork Guadalupe River 27.0
END DESCRIPTION:
XS GIS Cut Line= 3
      1853825.02     13924475.01        1854825.       13924975.
      1855824.96     13925274.99
#Sta/Elev= 30
    3882  1909.9  3901.7 1908.16  4052.5 1889.98  4069.3 1878.22  4074.8 1880.76
  4091.6 1858.78  4097.2 1859.94    4114 1846.35  4119.6 1847.77  4136.3 1835.11
  4164.3  1826.1  4172.7 1817.45  4222.6 1811.97  4331.1 1809.09  4341.9 1809.02
  4709.3 1806.97  4823.8 1792.54  4873.4 1792.36  4985.2 1786.08  4986.7 1785.08
  5058.4 1786.08  5108.9 1800.45  5186.8 1807.53  5594.6 1809.89  5696.5 1809.51
  5752.6 1820.34  5824.5 1853.86  5851.8 1872.24  5917.9 1902.49    6044 1926.82
#Mann= 14 ,-1 , 0
    3882      .1       0  3901.7    .035       0  4222.6      .1       0
  4331.1     .07       0  4341.9      .1       0  4823.8     .07       0
  4873.4      .1       0  4985.2     .05       0  5058.4      .1       0
  5108.9    .035       0  5186.8     .07       0  5594.6    .035       0
  5696.5     .07       0  5824.5      .1       0
Bank Sta=4985.2,5058.4
XS Rating Curve= 0 ,0
Exp/Cntr=0.3,0.1

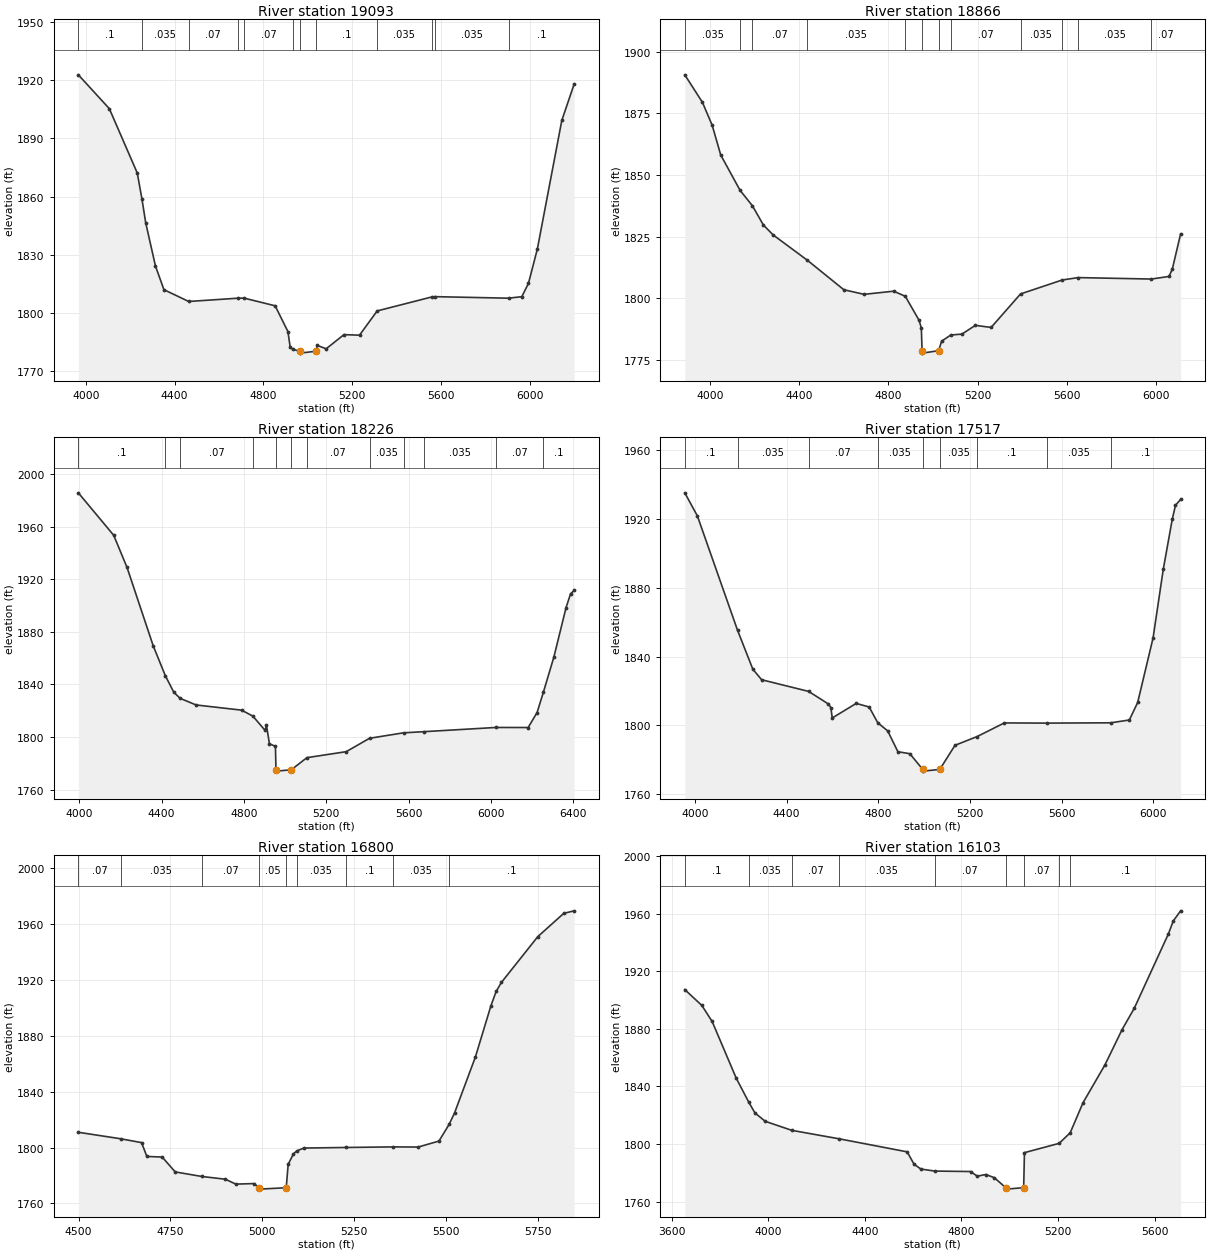
Type RM Length L Ch R = 1 ,19093   ,227,227,227
BEGIN DESCRIPTION:
South Fork Guadalupe River 26.0
END DESCRIPTION:
XS GIS Cut Line= 3
      1853674.98     13924924.99      1854598.91     13925422.76
      1855780.46      13925377.5
#Sta/Elev= 30
  3966.5 1922.65    4106 1905.24  4231.8  1872.1  4252.9  1858.7  4269.9 1846.42
  4313.7 1824.23  4351.8 1812.05  4463.4 1805.98  4683.5 1807.66  4712.4 1807.71
  4852.5 1803.75  4909.9 1790.48  4920.4  1782.3    4933 1781.29  4963.6 1780.39
  4965.1 1779.39  5036.8 1780.39  5042.1 1783.36  5082.1 1781.63  5162.2 1788.91
  5232.2 1788.63  5311.8 1801.12  5556.3 1808.27  5571.9 1808.46  5902.9 1807.67
  5962.8 1808.45  5992.8 1815.34  6032.8 1833.03  6142.9 1899.22  6198.4 1917.89
#Mann= 12 ,-1 , 0
  3966.5      .1       0  4252.9    .035       0  4463.4     .07       0
  4683.5      .1       0  4712.4     .07       0    4933      .1       0
  4963.6     .05       0  5036.8      .1       0  5311.8    .035       0
  5556.3     .07       0  5571.9    .035       0  5902.9      .1       0
Bank Sta=4963.6,5036.8
XS Rating Curve= 0 ,0
Exp/Cntr=0.3,0.1

Type RM Length L Ch R = 1 ,18866   ,640,640,640
BEGIN DESCRIPTION:
Mapping XS 97d413a1
END DESCRIPTION:
XS GIS Cut Line= 3
      1853528.54     13926076.75      1854423.95     13925591.52
       1855616.8     13925435.06
#Sta/Elev= 30
  3887.9  1890.7  3967.1 1879.49  4010.8 1870.16  4048.9 1858.12  4135.6 1843.76
    4191 1837.47    4240 1829.68  4283.8 1825.64  4436.9 1815.37  4600.4 1803.38
  4691.4 1801.51  4823.9 1802.79  4875.8 1800.71  4937.7 1790.93  4947.7 1787.82
    4951 1778.62  4952.5 1777.62  5025.2 1778.62  5038.5 1782.47  5079.8 1784.99
  5129.3 1785.34  5189.8  1788.9  5260.4 1788.06  5392.2 1801.67    5579 1807.34
  5650.5 1808.31  5978.4 1807.72  6057.2 1808.78  6071.8 1811.64  6109.4 1826.08
#Mann= 12 ,-1 , 0
  3887.9    .035       0  4135.6      .1       0    4191     .07       0
  4436.9    .035       0  4875.8      .1       0    4951     .05       0
  5025.2      .1       0  5079.8     .07       0  5392.2    .035       0
    5579     .07       0  5650.5    .035       0  5978.4     .07       0
Bank Sta=4951,5025.2
XS Rating Curve= 0 ,0
Exp/Cntr=0.3,0.1

Type RM Length L Ch R = 1 ,18226   ,709,709,709
BEGIN DESCRIPTION:
South Fork Guadalupe River 25.0
END DESCRIPTION:
XS GIS Cut Line= 3
      1853774.99     13926775.01        1854575.       13926175.
      1855806.26     13925492.05
#Sta/Elev= 30
  3995.8  1985.8  4167.7 1953.48  4232.3 1929.05  4359.4 1869.43  4418.3 1846.66
  4459.4 1834.12    4490 1829.45  4567.7 1824.41  4788.5 1820.47  4843.3 1815.94
  4903.1 1805.02  4909.4 1809.03  4923.9 1794.96  4953.1 1792.85  4955.6 1775.07
  4957.1 1774.07  5029.8 1775.07    5106 1784.32  5296.8 1788.87    5410 1799.06
  5575.2 1803.21  5675.7  1804.1  6024.3 1807.29  6180.3 1807.24  6223.8 1818.66
  6253.9 1833.89    6305 1860.68  6364.6 1898.54  6386.3 1908.95  6403.8 1911.55
#Mann= 12 ,-1 , 0
  3995.8      .1       0  4418.3    .035       0    4490     .07       0
  4843.3    .035       0  4955.6    .035       0  5029.8    .035       0
    5106     .07       0    5410    .035       0  5575.2     .07       0
  5675.7    .035       0  6024.3     .07       0  6253.9      .1       0
Bank Sta=4955.6,5029.8
XS Rating Curve= 0 ,0
Exp/Cntr=0.3,0.1

Type RM Length L Ch R = 1 ,17517   ,717,717,717
BEGIN DESCRIPTION:
South Fork Guadalupe River 24.0
END DESCRIPTION:
XS GIS Cut Line= 3
      1854074.99       13926875.        1855075.       13926575.
      1856075.02     13926074.99
#Sta/Elev= 30
  3956.2 1935.24    4011 1921.81  4186.2 1855.29  4252.9 1832.65  4291.2 1826.53
  4496.2 1819.74  4582.6 1812.41  4593.1 1810.34  4599.2 1804.29  4703.6 1812.76
  4760.1 1810.67  4797.9 1801.45    4841 1796.77  4885.4 1784.66  4937.6  1783.5
  4993.8 1774.37  4995.3 1773.37  5068.1 1774.37  5134.4 1788.39  5231.3  1793.5
  5349.6 1801.41    5535  1801.3  5813.6 1801.48  5894.7 1803.11    5931 1813.29
  5998.1  1850.8  6042.8 1890.88  6081.9 1919.91  6095.9    1928  6118.3 1931.44
#Mann= 9 ,-1 , 0
  3956.2      .1       0  4186.2    .035       0  4496.2     .07       0
  4797.9    .035       0  4993.8    .035       0  5068.1    .035       0
  5231.3      .1       0    5535    .035       0  5813.6      .1       0
Bank Sta=4993.8,5068.1
XS Rating Curve= 0 ,0
Exp/Cntr=0.3,0.1

Type RM Length L Ch R = 1 ,16800   ,697,697,697
BEGIN DESCRIPTION:
South Fork Guadalupe River 23.0
END DESCRIPTION:
XS GIS Cut Line= 3
      1855325.02     13927074.99        1855725.       13926775.
      1856324.99     13926175.01
#Sta/Elev= 30
  4499.4 1810.95  4615.1 1806.28  4671.3 1803.55  4685.8 1793.66  4727.5 1793.21
  4762.9 1782.58  4835.7  1779.3  4899.4 1777.35  4927.5 1773.85  4977.5 1774.24
  4990.5 1771.26    4992 1770.26  5064.8 1771.26  5070.1    1788  5084.2 1795.39
  5092.9  1797.5  5112.5 1799.66    5228 1800.07  5356.5 1800.49  5423.6 1800.38
  5480.2 1804.65  5507.7 1816.53  5522.6 1824.77  5579.2 1864.76  5621.6 1901.55
  5635.8 1911.78  5649.9 1918.16  5748.9 1950.94  5819.6 1967.64  5847.9 1969.45
#Mann= 9 ,-1 , 0
  4499.4     .07       0  4615.1    .035       0  4835.7     .07       0
  4990.5     .05       0  5064.8     .07       0  5092.9    .035       0
    5228      .1       0  5356.5    .035       0  5507.7      .1       0
Bank Sta=4990.5,5064.8
XS Rating Curve= 0 ,0
Exp/Cntr=0.3,0.1

Type RM Length L Ch R = 1 ,16103   ,728,728,728
BEGIN DESCRIPTION:
South Fork Guadalupe River 22.0
END DESCRIPTION:
XS GIS Cut Line= 3
        1855425.       13927975.        1856325.       13926975.
        1856425.     13926274.97
#Sta/Elev= 30
  3654.6 1907.26  3725.2 1896.25  3767.8 1885.13  3867.2 1845.87  3918.8 1829.26
    3945 1821.62  3987.6 1815.81  4097.5 1809.54  4292.5  1803.7  4575.1 1794.61
  4603.5 1786.04  4631.9 1782.67  4689.7 1781.26  4837.4 1780.95  4865.4 1777.73
  4900.9 1778.88  4936.1 1776.65    4983 1769.73  4984.5 1768.73  5057.4 1769.73
  5060.6 1794.06  5204.3 1800.51    5250 1807.84    5303 1828.68  5393.9    1855
  5464.6 1879.42  5515.1 1894.25  5656.6 1945.97  5676.8 1954.96  5707.1 1961.94
#Mann= 9 ,-1 , 0
  3654.6      .1       0  3918.8    .035       0  4097.5     .07       0
  4292.5    .035       0  4689.7     .07       0    4983     .05       0
  5057.4     .07       0  5204.3    .035       0    5250      .1       0
Bank Sta=4983,5057.4
XS Rating Curve= 0 ,0
Exp/Cntr=0.3,0.1

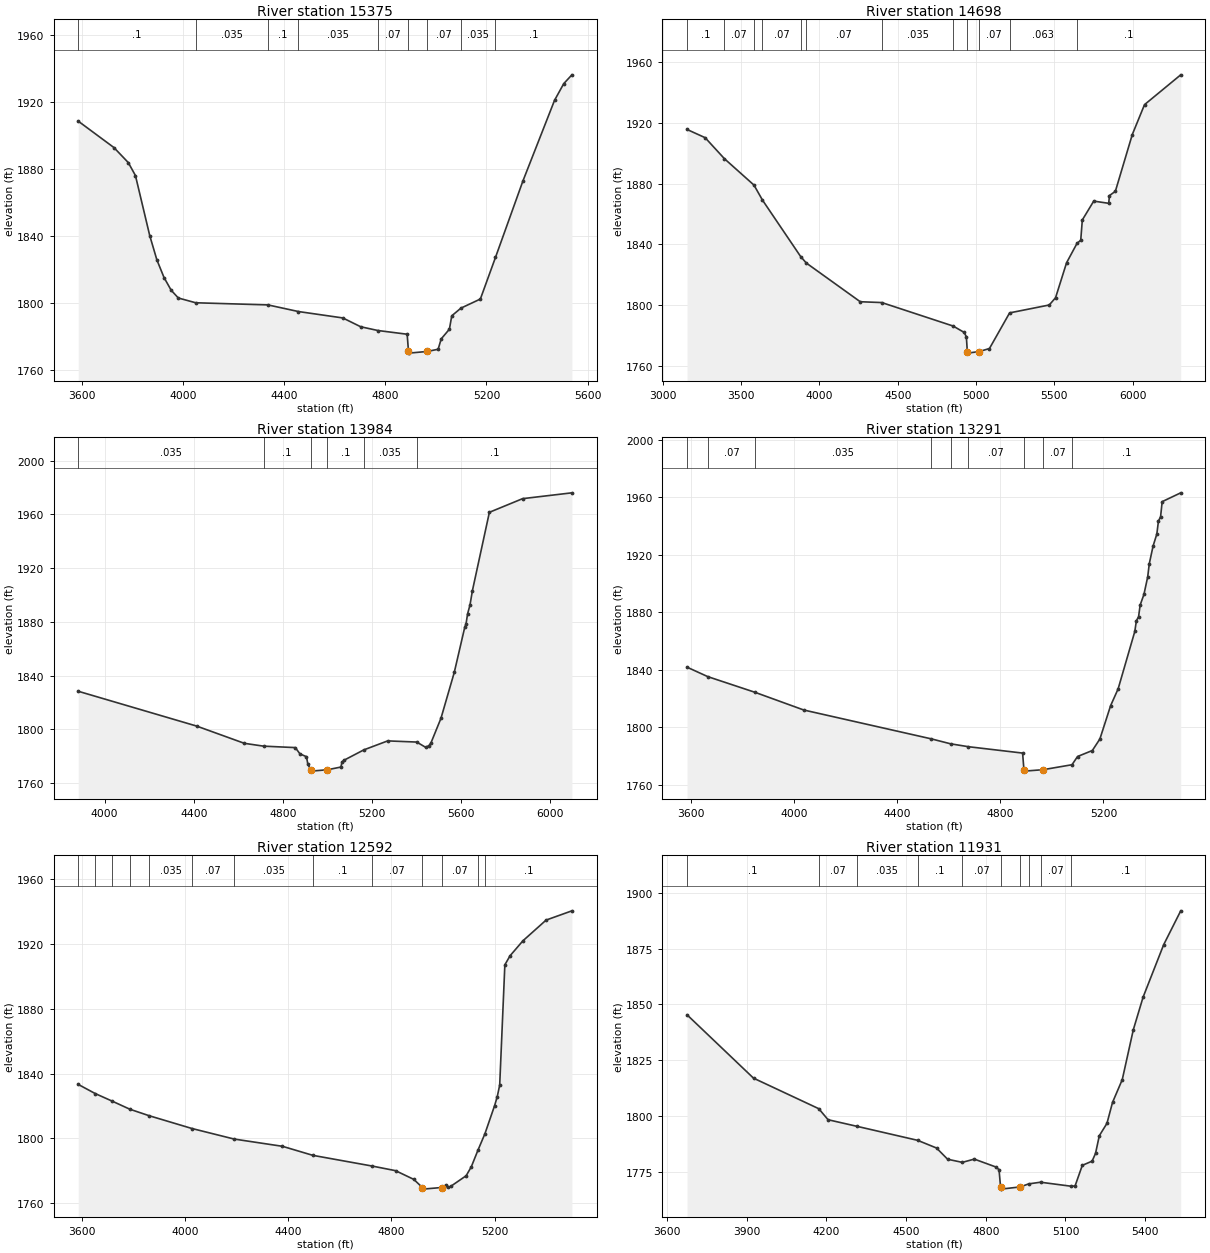
Type RM Length L Ch R = 1 ,15375   ,677,677,677
BEGIN DESCRIPTION:
South Fork Guadalupe River 21.0
END DESCRIPTION:
XS GIS Cut Line= 3
        1855925.       13928325.        1856925.       13927325.
      1857124.99     13926825.03
#Sta/Elev= 30
  3585.5 1908.38  3726.9 1892.59  3783.5 1883.64  3811.8 1875.91  3868.3 1840.07
  3896.6 1825.55  3924.9    1815  3953.2 1807.41  3981.5 1802.78  4050.1 1799.94
    4336 1798.66  4456.5  1794.7    4632 1790.88  4702.7 1785.62  4770.5 1783.38
  4886.6 1781.15  4891.8 1770.87  4893.3 1769.87  4966.2 1770.87  5009.1 1772.19
  5021.3 1778.39  5053.6 1784.16    5063 1792.16  5099.3 1796.74  5176.1 1802.17
  5235.9 1827.03  5344.4 1872.66  5469.6 1920.85  5505.9 1930.78  5538.2 1936.04
#Mann= 9 ,-1 , 0
  3585.5      .1       0  4050.1    .035       0    4336      .1       0
  4456.5    .035       0  4770.5     .07       0  4891.8     .05       0
  4966.2     .07       0  5099.3    .035       0  5235.9      .1       0
Bank Sta=4891.8,4966.2
XS Rating Curve= 0 ,0
Exp/Cntr=0.3,0.1

Type RM Length L Ch R = 1 ,14698   ,714,714,714
BEGIN DESCRIPTION:
South Fork Guadalupe River 20.0
END DESCRIPTION:
XS GIS Cut Line= 4
      1856292.18     13929175.31        1857425.       13927725.
        1857325.       13926725.      1857304.77     13926418.95
#Sta/Elev= 30
  3154.7 1915.75  3270.3 1910.33  3392.9 1896.54  3582.1 1879.11  3636.4 1869.22
  3879.9 1832.09  3916.3 1827.78  4260.6  1802.3  4397.9 1801.76  4853.8 1786.29
  4923.5 1782.13    4938 1779.26  4944.2 1769.46  4945.7 1768.46  5018.6 1769.46
  5085.4 1771.49  5214.2 1794.96  5467.3 1800.16  5507.5 1804.94  5577.9 1827.99
  5644.3  1840.7  5668.3 1842.83  5678.4 1856.17  5751.2 1868.57  5846.7 1867.12
  5851.7 1872.22  5889.4 1875.03  5997.5 1912.42  6075.5 1932.09  6306.7 1951.73
#Mann= 12 ,-1 , 0
  3154.7      .1       0  3392.9     .07       0  3582.1      .1       0
  3636.4     .07       0  3879.9      .1       0  3916.3     .07       0
  4397.9    .035       0  4853.8     .07       0  4944.2     .05       0
  5018.6     .07       0  5214.2    .063       0  5644.3      .1       0
Bank Sta=4944.2,5018.6
XS Rating Curve= 0 ,0
Exp/Cntr=0.3,0.1

Type RM Length L Ch R = 1 ,13984   ,693,693,693
BEGIN DESCRIPTION:
South Fork Guadalupe River 19.0
END DESCRIPTION:
XS GIS Cut Line= 4
      1857313.46     13928826.84        1857975.       13927925.
        1858675.       13927625.      1858970.29      13927460.2
#Sta/Elev= 30
  3881.2  1828.4  4413.5 1802.47  4627.6 1789.64  4714.1 1787.53  4856.5 1786.46
  4877.4 1781.81  4906.7 1779.66  4912.9 1774.15  4925.7 1769.94  4927.2 1768.94
  5000.3 1769.94  5061.3 1771.97  5066.8 1775.81  5075.8 1777.09  5164.5 1784.77
  5271.7 1791.45  5402.3 1790.58  5442.1 1786.66  5456.6 1787.87  5465.7  1789.8
    5511 1808.26  5570.8 1842.42    5618 1876.12  5623.4 1878.24  5630.7 1886.03
  5641.6 1892.73  5652.4 1903.37  5728.6 1961.63  5877.8 1971.79  6099.4 1976.13
#Mann= 6 ,-1 , 0
  3881.2    .035       0  4714.1      .1       0  4925.7     .05       0
  5000.3      .1       0  5164.5    .035       0  5402.3      .1       0
Bank Sta=4925.7,5000.3
XS Rating Curve= 0 ,0
Exp/Cntr=0.3,0.1

Type RM Length L Ch R = 1 ,13291   ,699,699,699
BEGIN DESCRIPTION:
South Fork Guadalupe River 18.0
END DESCRIPTION:
XS GIS Cut Line= 3
      1857474.99     13929175.01        1858475.       13928175.
      1858774.99     13927775.02
#Sta/Elev= 30
  3585.4 1841.73    3666 1835.15  3848.7 1824.27    4038 1811.95  4532.4 1791.89
  4607.3 1788.44  4676.5 1786.43  4886.5    1782  4891.6 1770.45  4893.1 1769.45
  4966.2 1770.45    5078  1773.9  5099.6 1779.62  5156.9 1783.79  5186.1 1791.79
  5227.8    1815  5256.9 1826.67  5321.5 1866.57  5327.7 1874.07  5336.1 1876.81
  5342.3 1884.94  5356.9 1892.31  5371.5  1904.5  5377.7 1913.71  5392.3 1925.91
  5406.9  1934.3  5413.2 1943.31  5421.5 1946.44  5427.7 1956.85  5499.6 1962.98
#Mann= 9 ,-1 , 0
  3585.4    .035       0    3666     .07       0  3848.7    .035       0
  4532.4    .063       0  4607.3    .035       0  4676.5     .07       0
  4891.6    .033       0  4966.2     .07       0    5078      .1       0
Bank Sta=4891.6,4966.2
XS Rating Curve= 0 ,0
Exp/Cntr=0.3,0.1

Type RM Length L Ch R = 1 ,12592   ,661,661,661
BEGIN DESCRIPTION:
South Fork Guadalupe River 17.0
END DESCRIPTION:
XS GIS Cut Line= 3
      1857925.01     13929474.99        1858925.       13928475.
        1858925.       13927975.
#Sta/Elev= 30
  3585.8 1833.34  3651.5 1827.72    3717 1823.06  3786.3 1818.02  3861.1 1814.02
  4026.9 1806.14  4190.5 1799.64  4377.7 1795.17  4495.6 1789.59  4725.6 1782.99
  4816.2 1780.14  4886.9 1774.77  4920.3 1769.76  4921.8 1768.76  4994.9 1769.76
    5010 1771.17    5020 1769.81    5030 1770.46    5090 1777.02    5110 1782.57
  5135.5  1792.7  5162.8 1802.96    5200 1820.15    5210 1825.42    5220 1832.92
    5240 1907.09    5260 1912.65    5310 1921.91    5400  1934.7    5500  1940.4
#Mann= 13 ,-1 , 0
  3585.8     .07       0  3651.5      .1       0    3717     .07       0
  3786.3      .1       0  3861.1    .035       0  4026.9     .07       0
  4190.5    .035       0  4495.6      .1       0  4725.6     .07       0
  4920.3     .05       0  4994.9     .07       0  5135.5    .033       0
  5162.8      .1       0
Bank Sta=4920.3,4994.9
XS Rating Curve= 0 ,0
Exp/Cntr=0.3,0.1

Type RM Length L Ch R = 1 ,11931   ,789,789,789
BEGIN DESCRIPTION:
South Fork Guadalupe River 16.0
END DESCRIPTION:
XS GIS Cut Line= 3
      1858524.97     13930025.03      1859283.96     13928979.47
      1859724.98     13928625.02
#Sta/Elev= 30
  3675.9 1845.36    3926 1817.04  4171.6 1803.38  4206.6 1798.45  4315.7 1795.49
  4543.9 1789.23  4614.8  1785.8  4656.5 1780.78  4711.7 1779.39    4757 1780.84
  4836.7 1777.38  4849.9 1776.15  4855.7 1768.42  4857.2 1767.42  4930.4 1768.42
  4961.2 1769.76  5006.1 1770.51  5120.2 1768.73    5136 1768.81  5163.3 1778.05
  5200.1 1779.93    5213 1783.36  5227.3 1791.29  5256.1 1796.84  5277.1 1806.21
  5313.7 1816.39  5355.3  1838.7  5392.1 1853.27  5469.6 1876.73  5533.7 1891.85
#Mann= 10 ,-1 , 0
  3675.9      .1       0  4171.6     .07       0  4315.7    .035       0
  4543.9      .1       0  4711.7     .07       0  4855.7     .05       0
  4930.4     .07       0  4961.2      .1       0  5006.1     .07       0
  5120.2      .1       0
Bank Sta=4855.7,4930.4
XS Rating Curve= 0 ,0
Exp/Cntr=0.3,0.1

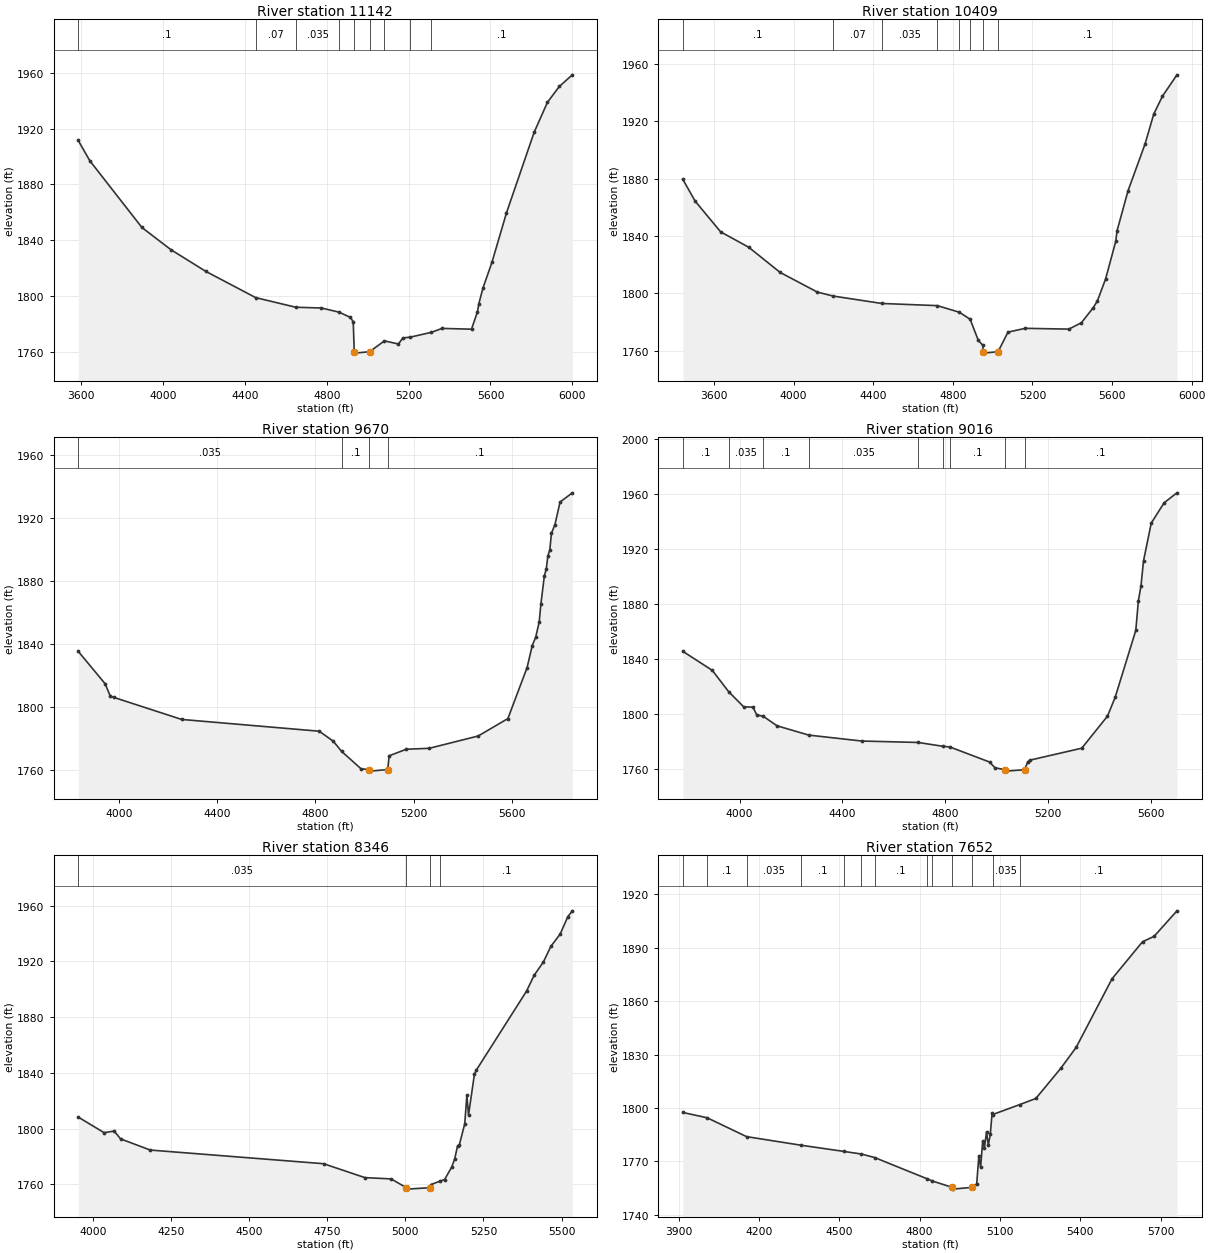
Type RM Length L Ch R = 1 ,11142   ,733,733,733
BEGIN DESCRIPTION:
South Fork Guadalupe River 15.0
END DESCRIPTION:
XS GIS Cut Line= 3
      1858525.03     13930574.97        1859525.       13929575.
      1860325.02     13928974.99
#Sta/Elev= 30
  3585.8 1911.44  3642.3 1896.94  3896.9 1849.11  4038.3 1833.24    4208 1817.76
  4452.8 1798.86  4648.4 1791.98  4773.7 1791.43  4861.2 1788.42  4915.1 1784.71
  4929.3  1781.6  4934.3  1760.1  4935.8  1759.1    5009  1760.1  5081.9 1767.88
    5150 1765.64  5171.9 1769.97  5208.2 1770.56  5311.3 1773.99  5363.5 1776.82
  5507.3 1776.25  5536.4 1788.74  5542.7 1794.29  5563.5 1805.87  5607.3 1824.22
  5678.1 1859.61  5813.5 1917.41  5878.1 1938.76  5936.4 1950.19    6000 1958.49
#Mann= 9 ,-1 , 0
  3585.8      .1       0  4452.8     .07       0  4648.4    .035       0
  4861.2      .1       0  4934.3    .035       0    5009      .1       0
  5081.9    .063       0  5208.2    .035       0  5311.3      .1       0
Bank Sta=4934.3,5009
XS Rating Curve= 0 ,0
Exp/Cntr=0.3,0.1

Type RM Length L Ch R = 1 ,10409   ,739,739,739
BEGIN DESCRIPTION:
South Fork Guadalupe River 14.0
END DESCRIPTION:
XS GIS Cut Line= 3
      1858719.28     13930602.59        1860125.       13929925.
      1860325.01     13929024.96
#Sta/Elev= 30
  3443.7 1879.45  3505.6 1864.29  3633.6 1842.93  3774.8 1832.19  3933.1 1814.62
  4119.6 1800.98    4199 1798.22  4443.4 1793.06  4722.2 1791.55  4833.4 1786.93
  4887.2 1782.04  4927.8  1767.5  4950.4 1763.98  4952.8 1759.49  4954.3 1758.49
  5027.5 1759.49  5077.2  1773.1  5164.3 1775.75  5383.2 1775.21    5446 1779.64
  5506.2 1790.21  5526.6 1794.89  5567.6 1810.09  5618.8 1836.34  5625.2 1843.62
  5680.3 1871.46  5766.1 1904.16  5809.6 1924.88  5853.2 1937.31  5926.2 1952.22
#Mann= 8 ,-1 , 0
  3443.7      .1       0    4199     .07       0  4443.4    .035       0
  4722.2     .07       0  4833.4      .1       0  4887.2     .07       0
  4952.8     .05       0  5027.5      .1       0
Bank Sta=4952.8,5027.5
XS Rating Curve= 0 ,0
Exp/Cntr=0.3,0.1

Type RM Length L Ch R = 1 ,9670    ,654,654,654
BEGIN DESCRIPTION:
South Fork Guadalupe River 13.0
END DESCRIPTION:
XS GIS Cut Line= 3
      1859814.87     13931248.53        1860625.       13930325.
      1861124.98     13929725.02
#Sta/Elev= 30
  3835.3 1835.38  3944.5 1814.84  3965.4 1807.06  3979.6 1806.18  4255.8 1792.16
  4815.6 1784.68  4872.6 1778.31  4906.4 1771.88  4985.5  1760.8  5019.3 1760.34
  5020.8 1759.34  5094.1 1760.34  5099.6 1769.07  5169.9 1773.26  5262.3 1773.82
  5461.5 1781.63  5582.5 1792.69  5660.6 1825.05  5681.5 1838.98  5695.8 1844.41
  5710.1 1854.23  5716.6 1865.15  5730.9 1883.38  5738.7 1887.67  5745.2 1896.04
  5753.1 1899.81  5759.6  1910.3  5773.9 1915.88  5794.7 1930.19  5844.8 1936.05
#Mann= 4 ,-1 , 0
  3835.3    .035       0  4906.4      .1       0  5019.3     .05       0
  5094.1      .1       0
Bank Sta=5019.3,5094.1
XS Rating Curve= 0 ,0
Exp/Cntr=0.3,0.1

Type RM Length L Ch R = 1 ,9016    ,670,670,670
BEGIN DESCRIPTION:
South Fork Guadalupe River 12.0
END DESCRIPTION:
XS GIS Cut Line= 3
        1859975.       13931575.        1860975.       13930875.
      1861675.04       13930875.
#Sta/Elev= 30
  3779.6  1845.6  3894.3 1831.74  3957.8 1816.21  4016.3 1805.21  4052.1    1805
  4066.9 1799.42  4093.1 1798.23  4145.8 1791.42  4269.3 1784.65  4475.4 1780.34
  4694.4  1779.3  4791.3 1776.49  4817.6 1776.02  4971.9 1765.06  4992.8 1760.87
  5032.8 1759.44  5034.3 1758.44  5107.7 1759.44  5120.3 1765.15  5130.3  1766.5
  5330.3 1775.13  5430.3 1798.46  5460.3 1812.27  5540.3 1860.85  5550.3  1882.3
  5560.3 1893.04  5570.3 1911.39  5600.3 1938.88  5650.3  1953.7  5700.3 1960.95
#Mann= 9 ,-1 , 0
  3779.6      .1       0  3957.8    .035       0  4093.1      .1       0
  4269.3    .035       0  4694.4      .1       0  4791.3    .035       0
  4817.6      .1       0  5032.8     .05       0  5107.7      .1       0
Bank Sta=5032.8,5107.7
XS Rating Curve= 0 ,0
Exp/Cntr=0.3,0.1

Type RM Length L Ch R = 1 ,8346    ,694,694,694
BEGIN DESCRIPTION:
South Fork Guadalupe River 11.0
END DESCRIPTION:
XS GIS Cut Line= 3
      1860224.97     13931725.01        1861225.       13931425.
      1861725.02     13931224.99
#Sta/Elev= 30
  3952.1 1808.24  4034.8 1797.09    4067  1798.2  4087.9 1792.59  4182.7 1784.59
  4737.8 1774.79    4870 1764.81  4954.4 1763.87  5003.1 1757.54  5004.6 1756.54
    5078 1757.54  5082.3 1759.86  5112.3  1762.4  5125.4 1763.39  5148.3 1772.39
  5157.7 1778.14  5167.1 1787.62  5172.5 1788.18    5190 1803.45  5196.8 1823.79
  5202.1 1809.78    5221    1839  5226.4 1841.73  5387.9 1898.66  5412.2 1910.02
  5441.8 1919.55    5466 1930.86  5495.6 1939.59  5519.9 1952.03  5534.7 1956.31
#Mann= 4 ,-1 , 0
  3952.1    .035       0  5003.1    .035       0    5078    .035       0
  5112.3      .1       0
Bank Sta=5003.1,5078
XS Rating Curve= 0 ,0
Exp/Cntr=0.3,0.1

Type RM Length L Ch R = 1 ,7652    ,688,688,688
BEGIN DESCRIPTION:
South Fork Guadalupe River 10.0
END DESCRIPTION:
XS GIS Cut Line= 3
      1860261.18     13932230.51        1861325.       13932025.
      1861917.24     13931546.95
#Sta/Elev= 30
    3916 1797.51  4006.7 1794.54  4153.9 1783.95  4356.8 1779.14  4517.3 1775.65
  4582.9 1774.18  4631.9 1772.22    4828 1760.29  4847.1 1759.07  4921.3 1755.49
  4922.8 1754.49  4996.2 1755.49  5013.1  1757.5  5021.1 1773.23  5027.5 1766.68
  5035.5 1781.49  5041.9 1777.83  5049.8 1786.63  5056.3 1779.12  5063.7  1785.2
  5070.7 1797.34  5072.7 1796.35  5174.5 1801.98  5233.8 1805.37  5326.5 1822.21
  5384.1 1833.99  5518.4 1872.57    5632 1893.32  5675.2 1896.35  5760.6 1910.68
#Mann= 13 ,-1 , 0
    3916    .035       0  4006.7      .1       0  4153.9    .035       0
  4356.8      .1       0  4517.3     .07       0  4582.9    .035       0
  4631.9      .1       0    4828    .035       0  4847.1     .07       0
  4921.3     .05       0  4996.2     .07       0  5072.7    .035       0
  5174.5      .1       0
Bank Sta=4921.3,4996.2
XS Rating Curve= 0 ,0
Exp/Cntr=0.3,0.1

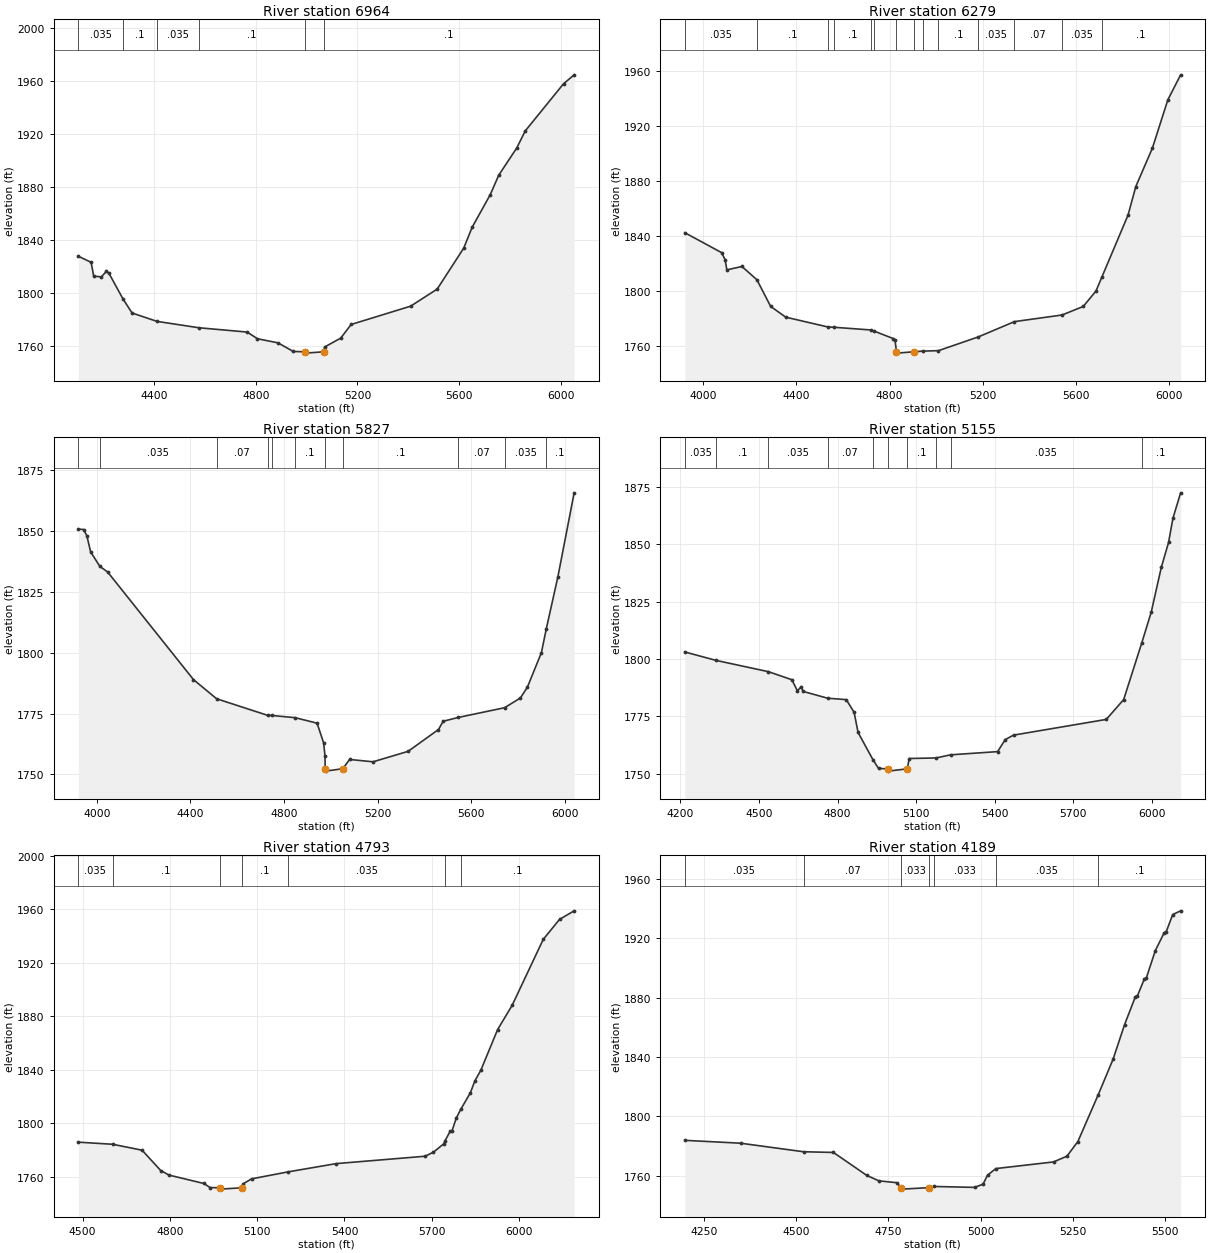
Type RM Length L Ch R = 1 ,6964    ,685,685,685
BEGIN DESCRIPTION:
South Fork Guadalupe River 9.0
END DESCRIPTION:
XS GIS Cut Line= 3
      1860224.99       13932525.        1861125.       13932625.
      1862125.02     13932324.99
#Sta/Elev= 30
  4102.4 1827.97  4152.7 1823.37  4162.8 1812.98    4193 1812.37  4213.1 1816.69
  4223.1 1814.98  4278.4 1795.61  4313.7 1785.13  4411.5 1778.82  4576.2    1774
  4766.5 1770.74  4806.7  1765.7  4887.2 1762.62  4947.6 1756.11  4992.2 1755.85
  4993.7 1754.85  5067.2 1755.85  5070.6 1759.44  5134.1 1766.18    5175 1776.46
    5409 1790.29  5513.4 1803.18  5617.8 1834.11  5650.9 1849.82  5722.2 1874.48
  5755.3 1889.08  5826.6 1909.76  5859.7 1922.54  6010.2 1958.11    6052 1964.86
#Mann= 6 ,-1 , 0
  4102.4    .035       0  4278.4      .1       0  4411.5    .035       0
  4576.2      .1       0  4992.2     .05       0  5067.2      .1       0
Bank Sta=4992.2,5067.2
XS Rating Curve= 0 ,0
Exp/Cntr=0.3,0.1

Type RM Length L Ch R = 1 ,6279    ,452,452,452
BEGIN DESCRIPTION:
South Fork Guadalupe River 8.0
END DESCRIPTION:
XS GIS Cut Line= 3
      1860124.99     13932624.99        1861025.       13933225.
      1862024.99       13933525.
#Sta/Elev= 30
  3922.2 1842.23    4080 1827.72    4095 1822.55  4102.5 1815.16  4167.1 1817.62
  4231.2 1808.01  4290.3 1788.56  4354.9 1780.72  4535.9 1773.57  4561.9 1773.36
  4719.7  1771.4  4733.7 1770.57  4816.1 1765.13  4823.6 1763.75  4829.7 1755.53
  4831.2 1754.53  4904.7 1755.53  4943.1    1756  5009.8 1756.33  5180.2 1766.32
  5335.5 1777.48  5539.3 1782.29  5630.3  1788.5  5685.1 1799.75  5709.9 1809.77
  5822.6  1855.1  5855.6 1875.77    5927 1903.89  5993.1 1938.99  6047.9  1957.2
#Mann= 14 ,-1 , 0
  3922.2    .035       0  4231.2      .1       0  4535.9    .035       0
  4561.9      .1       0  4719.7    .035       0  4733.7      .1       0
  4829.7     .05       0  4904.7      .1       0  4943.1     .07       0
  5009.8      .1       0  5180.2    .035       0  5335.5     .07       0
  5539.3    .035       0  5709.9      .1       0
Bank Sta=4829.7,4904.7
XS Rating Curve= 0 ,0
Exp/Cntr=0.3,0.1

Type RM Length L Ch R = 1 ,5827    ,672,672,672
BEGIN DESCRIPTION:
South Fork Guadalupe River 7.0
END DESCRIPTION:
XS GIS Cut Line= 3
        1859825.       13933075.      1860809.38     13933575.19
      1861825.01       13933575.
#Sta/Elev= 30
  3920.6 1850.68    3943 1850.51  3956.8    1848  3973.4 1841.29  4012.7 1835.36
  4045.8 1833.09  4412.9 1788.91  4511.9 1781.05  4730.9 1774.22  4747.6 1774.19
  4847.4  1773.3  4941.3 1771.04  4969.3 1762.95    4975 1757.75  4976.3 1752.36
  4977.8 1751.36  5051.3 1752.36  5080.4 1756.15  5180.4 1755.19  5330.4 1759.47
  5460.4 1768.44  5480.4 1771.83  5545.7  1773.4  5742.9 1777.38  5810.4 1781.36
  5840.4 1785.79  5900.4 1799.99  5921.4 1809.83  5970.4  1830.9  6040.4 1865.56
#Mann= 11 ,-1 , 0
  3920.6     .07       0  4012.7    .035       0  4511.9     .07       0
  4730.9      .1       0  4747.6     .07       0  4847.4      .1       0
  4976.3     .05       0  5051.3      .1       0  5545.7     .07       0
  5742.9    .035       0  5921.4      .1       0
Bank Sta=4976.3,5051.3
XS Rating Curve= 0 ,0
Exp/Cntr=0.3,0.1

Type RM Length L Ch R = 1 ,5155    ,362,362,362
BEGIN DESCRIPTION:
South Fork Guadalupe River 6.1
END DESCRIPTION:
XS GIS Cut Line= 3
      1860221.57     13934607.32      1861014.88      13934080.8
      1861849.33     13933648.12
#Sta/Elev= 30
  4217.1 1803.08  4337.2 1799.39  4536.4 1794.49  4625.7 1790.99  4646.8 1786.16
  4661.8    1788  4667.8 1785.94  4761.7 1782.96  4833.3 1782.33  4863.3 1776.78
  4878.3 1768.05  4934.9 1756.23  4956.5 1752.38  4991.1 1752.21  4992.6 1751.21
  5066.2 1752.21  5073.4  1756.7  5176.3 1756.95  5231.2 1758.31  5410.8  1759.7
  5439.7 1764.92  5471.5 1766.88  5825.5 1773.72  5891.9 1782.36  5960.4 1806.84
  5996.9 1820.35  6035.5 1839.91  6063.3  1850.8  6079.8 1861.26  6109.2 1872.35
#Mann= 10 ,-1 , 0
  4217.1    .035       0  4337.2      .1       0  4536.4    .035       0
  4761.7     .07       0  4934.9      .1       0  4991.1     .05       0
  5066.2      .1       0  5176.3    .063       0  5231.2    .035       0
  5960.4      .1       0
Bank Sta=4991.1,5066.2
XS Rating Curve= 0 ,0
Exp/Cntr=0.3,0.1

Type RM Length L Ch R = 1 ,4793    ,604,604,604
BEGIN DESCRIPTION:
South Fork Guadalupe River 6.0
END DESCRIPTION:
XS GIS Cut Line= 3
      1860775.03     13934674.97      1861138.42     13934336.32
        1862075.       13933575.
#Sta/Elev= 30
  4485.5 1785.98    4603 1784.42  4704.6 1779.98  4768.6 1764.79  4796.9 1761.38
  4917.1  1755.1  4938.1 1752.06  4971.5 1751.89    4973 1750.89  5046.6 1751.89
  5052.2 1754.93  5080.9 1758.57    5207 1763.82  5371.8 1769.96  5677.1 1775.47
  5705.8 1778.53    5741 1784.71    5746 1787.19  5763.3  1794.2  5769.7 1794.55
  5784.1 1803.95  5799.3 1810.43  5832.5 1822.83    5848 1831.74  5868.8 1839.85
  5926.3 1870.17  5975.9 1888.14  6082.9 1937.48  6138.9 1952.45  6189.2 1958.85
#Mann= 7 ,-1 , 0
  4485.5    .035       0    4603      .1       0  4971.5     .05       0
  5046.6      .1       0    5207    .035       0    5746     .07       0
  5799.3      .1       0
Bank Sta=4971.5,5046.6
XS Rating Curve= 0 ,0
Exp/Cntr=0.3,0.1

Type RM Length L Ch R = 1 ,4189    ,684,684,684
BEGIN DESCRIPTION:
South Fork Guadalupe River 5.0
END DESCRIPTION:
XS GIS Cut Line= 3
      1860825.03       13934775.        1861625.       13934675.
      1862124.99       13934475.
#Sta/Elev= 30
  4197.6 1783.73  4348.7  1781.8  4519.6 1776.03  4600.7 1775.56  4691.4 1760.02
  4724.1 1756.39    4772 1755.17  4784.8 1751.81  4786.3 1750.81  4859.9 1751.81
  4872.9 1752.61  4983.6 1751.98  5006.5 1754.17  5018.6 1760.21  5041.3 1764.68
  5197.7 1769.16    5234 1773.05  5263.6  1782.9  5318.8 1814.47  5359.2 1838.52
  5390.2 1861.74  5419.8 1880.75  5425.2  1881.3    5444 1892.62  5449.4 1893.38
  5473.7 1911.75  5497.9  1923.9  5503.3 1924.49  5520.8 1936.05  5542.3 1938.58
#Mann= 7 ,-1 , 0
  4197.6    .035       0  4519.6     .07       0  4784.8    .033       0
  4859.9     .07       0  4872.9    .033       0  5041.3    .035       0
  5318.8      .1       0
Bank Sta=4784.8,4859.9
XS Rating Curve= 0 ,0
Exp/Cntr=0.3,0.1