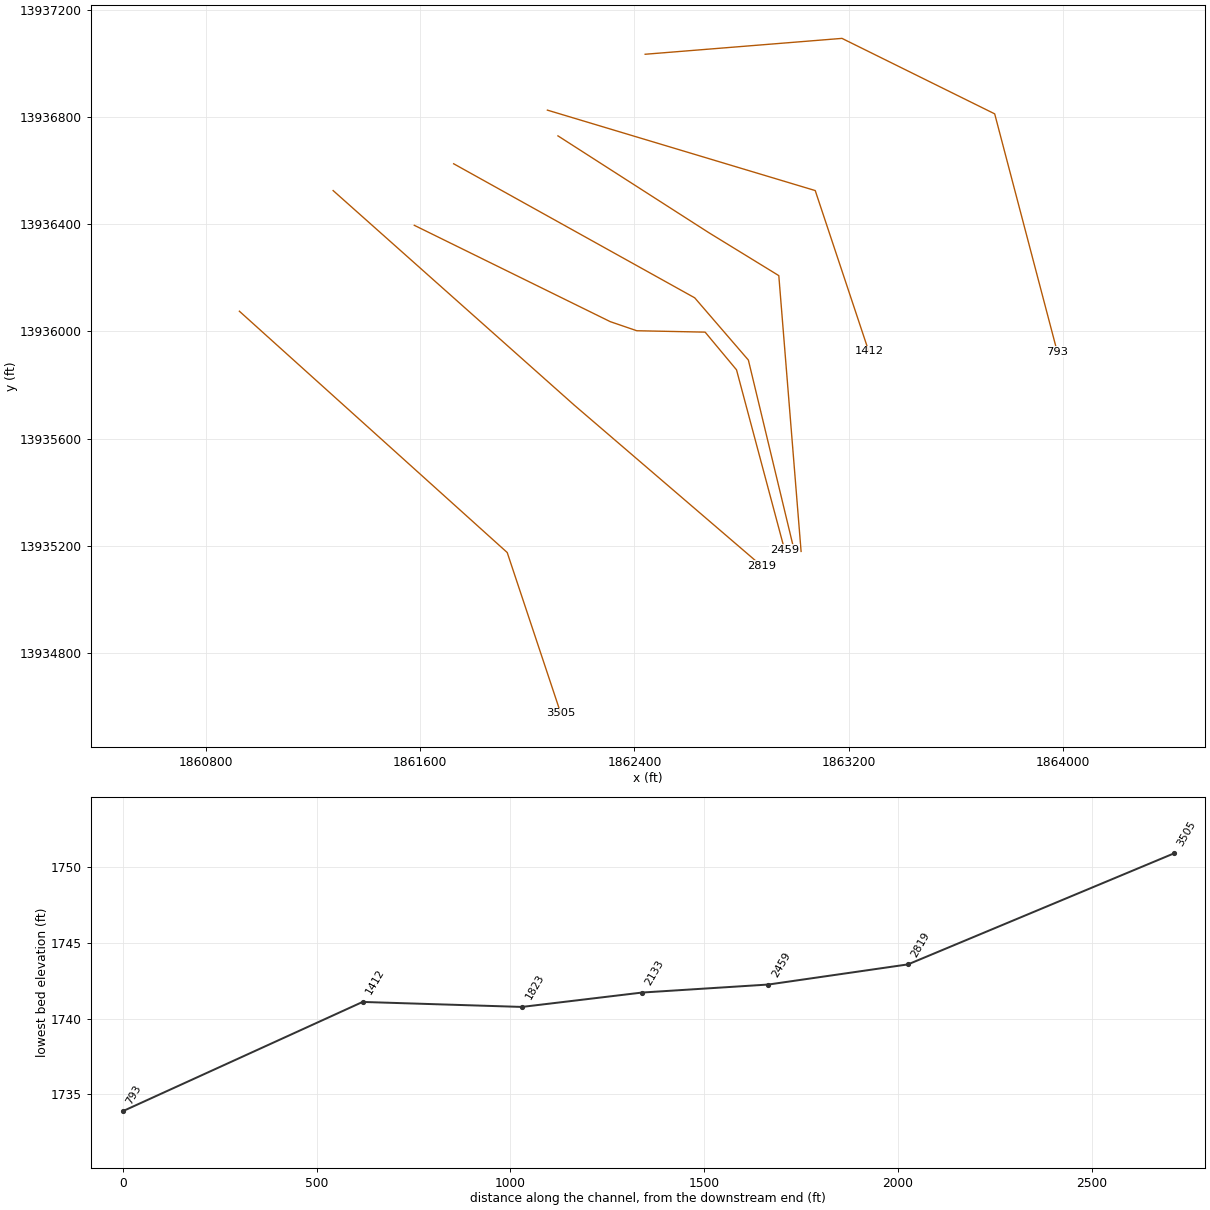
HEC-RAS study South Fork Guadalupe River.prj: South Fork Guadalupe River Base Level Engineering

--- South Fork Guadalupe River.g01 (geometry) --- (continued)

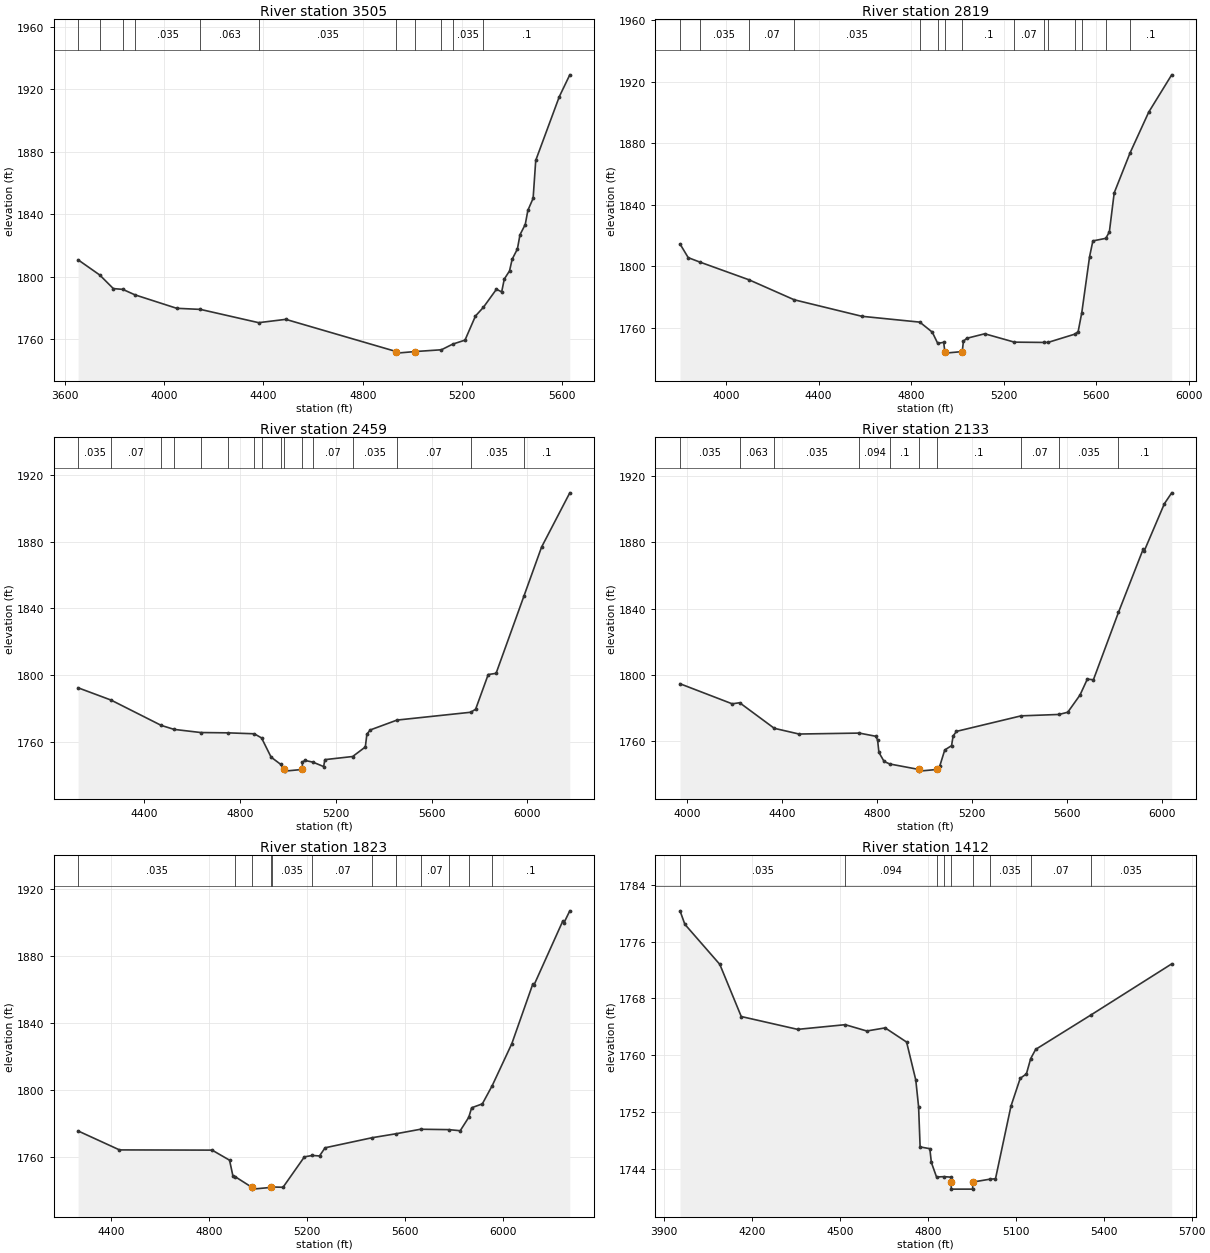
Type RM Length L Ch R = 1 ,3505    ,686,686,686
BEGIN DESCRIPTION:
South Fork Guadalupe River 4.0
END DESCRIPTION:
XS GIS Cut Line= 3
      1860924.99     13936075.01        1861925.       13935175.
      1862124.99     13934575.03
#Sta/Elev= 30
  3654.6 1810.74  3741.3 1801.05  3796.2 1792.31  3834.3  1791.8  3883.3 1788.29
  4051.1 1779.67  4146.7 1778.96  4380.8 1770.45  4489.9 1772.58  4934.4 1751.92
  4935.9 1750.92  5009.5 1751.92  5116.2 1753.08  5161.5  1756.7  5210.8 1759.25
    5253 1774.72  5284.8 1780.29  5337.3 1791.88  5358.4 1790.19  5368.9 1798.42
    5390 1803.66  5400.5 1811.11  5421.6 1817.68  5432.1 1826.85  5453.2  1833.4
  5463.8  1842.5  5484.9 1850.21  5495.4 1874.52  5590.3 1915.44  5632.4 1929.38
#Mann= 11 ,-1 , 0
  3654.6      .1       0  3741.3    .035       0  3834.3    .063       0
  3883.3    .035       0  4146.7    .063       0  4380.8    .035       0
  4934.4     .05       0  5009.5    .035       0  5116.2    .033       0
  5161.5    .035       0  5284.8      .1       0
Bank Sta=4934.4,5009.5
XS Rating Curve= 0 ,0
Exp/Cntr=0.3,0.1

Type RM Length L Ch R = 1 ,2819    ,360,360,360
BEGIN DESCRIPTION:
South Fork Guadalupe River 3.0
END DESCRIPTION:
XS GIS Cut Line= 3
      1861275.01     13936524.99        1862175.       13935725.
        1862875.       13935125.
#Sta/Elev= 30
  3800.8 1814.55  3836.3 1805.65  3885.4 1802.85  4099.2 1791.25  4294.6 1778.27
  4587.3 1767.53  4837.8 1763.74  4891.6 1757.23  4915.2 1749.94    4941  1750.6
    4946 1744.59  4947.5 1743.59  5021.2 1744.59  5026.3 1751.35  5040.6 1753.22
  5118.5 1756.17  5246.7 1750.73  5374.8 1750.54  5392.4 1750.57  5508.4 1755.95
  5522.4 1757.58  5538.1 1769.85  5571.8 1806.27  5586.1 1816.53  5641.9 1818.21
  5657.4 1822.41  5678.3 1847.76  5746.4 1873.58  5827.6 1900.26  5926.9  1924.5
#Mann= 15 ,-1 , 0
  3800.8    .094       0  3885.4    .035       0  4099.2     .07       0
  4294.6    .035       0  4837.8    .063       0  4915.2      .1       0
    4946     .05       0  5021.2      .1       0  5246.7     .07       0
  5374.8     .12       0  5392.4    .035       0  5508.4     .07       0
  5538.1    .035       0  5641.9    .094       0  5746.4      .1       0
Bank Sta=4946,5021.2
XS Rating Curve= 0 ,0
Exp/Cntr=0.3,0.1

Type RM Length L Ch R = 1 ,2459    ,326,326,326
BEGIN DESCRIPTION:
South Fork Guadalupe River 2.1
END DESCRIPTION:
XS GIS Cut Line= 6
      1861577.97     13936395.45      1862309.76     13936036.07
      1862408.72     13936002.22      1862663.93     13935997.01
      1862781.11     13935856.38       1862960.4     13935186.02
#Sta/Elev= 30
  4124.9 1792.24  4262.3 1784.88  4471.7  1769.7  4525.3  1767.3  4636.9 1765.41
  4748.5 1765.23  4860.2 1764.66  4890.5 1762.17  4930.3 1750.66    4970 1746.36
  4985.2 1743.26  4986.7 1742.26  5060.4 1743.26    5061 1747.51    5071 1748.69
  5105.3 1747.64  5149.7 1744.98  5154.7 1749.15  5270.8 1751.03  5323.6 1756.75
  5330.2 1764.48  5344.5 1766.98  5455.8 1772.88  5763.8 1777.58    5784 1779.41
  5836.5 1800.21  5869.3 1800.91  5985.2 1847.12  6059.2 1876.65    6177  1909.2
#Mann= 16 ,-1 , 0
  4124.9    .035       0  4262.3     .07       0  4471.7    .035       0
  4525.3     .07       0  4636.9    .035       0  4748.5    .063       0
  4860.2    .094       0  4890.5    .063       0    4970      .1       0
  4985.2     .05       0  5060.4      .1       0  5105.3     .07       0
  5270.8    .035       0  5455.8     .07       0  5763.8    .035       0
  5985.2      .1       0
Bank Sta=4985.2,5060.4
XS Rating Curve= 0 ,0
Exp/Cntr=0.3,0.1

Type RM Length L Ch R = 1 ,2133    ,310,310,310
BEGIN DESCRIPTION:
South Fork Guadalupe River 2.0
END DESCRIPTION:
XS GIS Cut Line= 4
      1861725.03     13936624.98        1862625.       13936125.
      1862825.38     13935892.84      1862997.18     13935179.65
#Sta/Elev= 30
  3970.5 1794.56  4190.1 1782.43  4221.6 1783.08  4367.3 1767.62  4471.5 1764.16
  4725.1 1764.73  4794.1 1762.82  4802.1 1760.64  4807.8 1753.03  4829.6 1747.59
  4853.2 1746.06  4976.2 1742.73  4977.7 1741.73  5051.4 1742.73  5064.2 1744.89
    5085 1754.53  5113.6 1757.13  5120.2    1763  5134.4 1765.77  5406.3 1775.15
  5565.9    1776  5602.8 1777.34  5654.2  1787.7  5685.1 1797.35  5710.8 1796.98
  5816.1 1837.67  5920.4 1875.99  5925.5 1875.11  6009.4 1903.38  6040.3    1910
#Mann= 10 ,-1 , 0
  3970.5    .035       0  4221.6    .063       0  4367.3    .035       0
  4725.1    .094       0  4853.2      .1       0  4976.2     .05       0
  5051.4      .1       0  5406.3     .07       0  5565.9    .035       0
  5816.1      .1       0
Bank Sta=4976.2,5051.4
XS Rating Curve= 0 ,0
Exp/Cntr=0.3,0.1

Type RM Length L Ch R = 1 ,1823    ,411,411,411
BEGIN DESCRIPTION:
Mapping XS c9779fc4
END DESCRIPTION:
XS GIS Cut Line= 4
      1862114.43       13936729.       1862678.1     13936367.71
        1862939.     13936207.78       1863022.2     13935179.08
#Sta/Elev= 30
  4264.7 1775.57  4433.6 1764.24  4811.8 1764.11    4883 1758.09  4896.9 1748.57
  4906.4 1748.18  4975.1 1741.78  4976.6 1740.78  5050.3 1741.78  5056.6 1742.07
  5101.4 1741.89  5188.6 1760.07  5221.1 1760.93  5250.3 1760.62  5273.1 1765.51
  5466.1 1771.56  5564.5 1773.94  5662.9  1776.6  5777.2 1776.37  5824.9 1775.72
  5859.8 1783.75  5871.5 1789.44  5915.2 1791.78  5955.7 1802.73  6035.6  1827.8
  6120.9 1863.31    6126  1862.8  6243.2 1900.96  6248.2 1899.98  6272.3 1907.24
#Mann= 12 ,-1 , 0
  4264.7    .035       0  4906.4      .1       0  4975.1     .05       0
  5050.3      .1       0  5056.6    .035       0  5221.1     .07       0
  5466.1    .035       0  5564.5     .12       0  5662.9     .07       0
  5777.2     .12       0  5859.8    .035       0  5955.7      .1       0
Bank Sta=4975.1,5050.3
XS Rating Curve= 0 ,0
Exp/Cntr=0.3,0.1

Type RM Length L Ch R = 1 ,1412    ,619,619,619
BEGIN DESCRIPTION:
South Fork Guadalupe River 1.0
END DESCRIPTION:
XS GIS Cut Line= 3
      1862074.98     13936825.01        1863075.       13936525.
        1863275.       13935925.
#Sta/Elev= 30
  3955.4 1780.34  3971.9 1778.44  4091.1 1772.79  4164.2 1765.44  4356.5 1763.63
  4518.7 1764.29  4592.3  1763.4  4654.9 1763.84    4728 1761.84  4759.3 1756.49
  4768.9 1752.71  4774.1 1747.06  4807.2 1746.81  4812.4 1744.87  4830.1 1742.82
  4855.4 1742.87  4878.5  1742.8  4879.2 1742.11  4880.7 1741.11  4952.9 1741.11
  4954.4 1742.11  5011.6 1742.51  5031.1 1742.57  5083.8  1752.8  5115.4 1756.73
  5136.5 1757.35  5151.1 1759.51  5168.1 1760.81  5356.2 1765.65  5631.9 1772.86
#Mann= 9 ,-1 , 0
  3955.4    .035       0  4518.7    .094       0  4830.1    .035       0
  4855.4      .1       0  4879.2     .05       0  4954.4      .1       0
  5011.6    .035       0  5151.1     .07       0  5356.2    .035       0
Bank Sta=4879.2,4954.4
XS Rating Curve= 0 ,0
Exp/Cntr=0.3,0.1

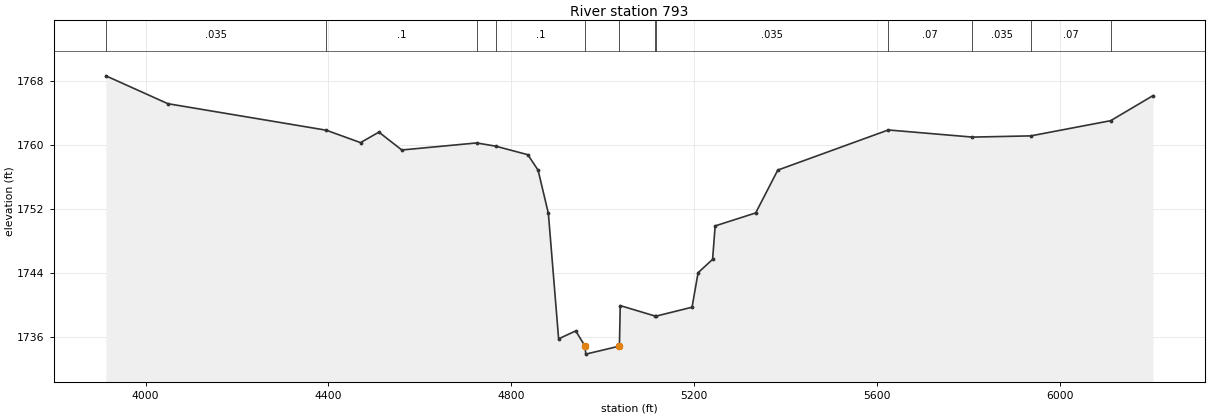
Type RM Length L Ch R = 1 ,793     ,0,0,0
BEGIN DESCRIPTION:
South Fork Guadalupe River 0.0
END DESCRIPTION:
XS GIS Cut Line= 4
      1862439.97     13937033.39      1863174.87     13937092.61
      1863745.03     13936811.14      1863978.41     13935924.58
#Sta/Elev= 30
  3913.3 1768.64  4048.8 1765.16  4395.2 1761.85  4470.1  1760.3  4510.3 1761.61
  4560.4 1759.38    4724 1760.26  4765.5 1759.86    4836 1758.79  4858.4 1756.86
  4880.9 1751.46  4903.3  1735.8  4940.7 1736.79  4961.1 1734.89  4962.6 1733.89
  5036.3 1734.89    5038 1739.95  5113.9 1738.65  5115.4 1738.62  5195.1 1739.75
  5208.3 1744.06    5240 1745.72  5245.6  1749.9  5334.2 1751.52  5382.6 1756.87
  5624.2 1761.88    5808 1760.99  5935.7 1761.14  6110.5 1763.04  6203.2 1766.17
#Mann= 12 ,-1 , 0
  3913.3    .035       0  4395.2      .1       0    4724    .035       0
  4765.5      .1       0  4961.1     .05       0  5036.3      .1       0
  5113.9    .063       0  5115.4    .035       0  5624.2     .07       0
    5808    .035       0  5935.7     .07       0  6110.5    .035       0
Bank Sta=4961.1,5036.3
XS Rating Curve= 0 ,0
Exp/Cntr=0.3,0.1

Chan Stop Cuts=-1
Use User Specified Reach Order=0
Composite Channel Slope=5