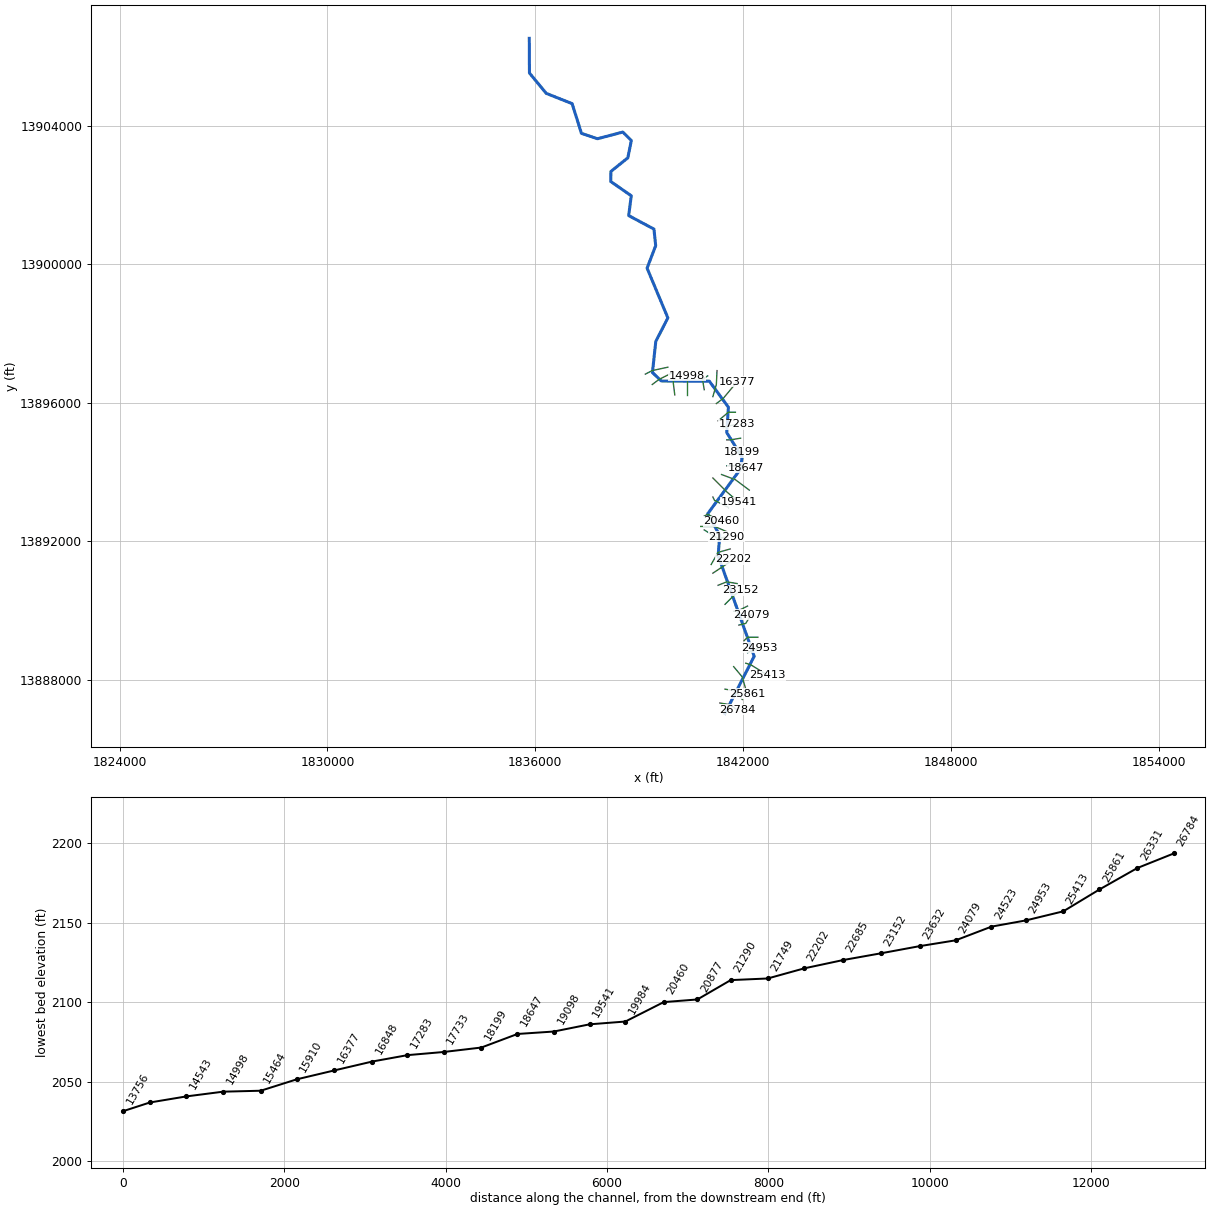
--- Spur Branch.prj (project) ---

Proj Title=Spur Branch Base Level Engineering
Current Plan=p01
Default Exp/Contr=0.3,0.1
English Units
Geom File=g01
Flow File=f01
Plan File=p01
BEGIN DESCRIPTION:
Spur Branch
END DESCRIPTION:

--- Spur Branch.p01 (plan) ---

Plan Title=Multiple Run
Short Identifier=Multiple
Geom File=g01
Flow File=f01
Subcritical Flow
K Sum by GR= 0
Std Step Tol= 0.01
Critical Tol= 0.01
Num of Std Step Trials= 20
Max Error Tol= 0.3
Flow Tol Ratio= 0.001
Split Flow NTrial= 30
Split Flow Tol= 0.02
Split Flow Ratio= 0.02
Log Output Level= 0
Friction Slope Method= 1
Unsteady Friction Slope Method= 2
Unsteady Bridges Friction Slope Method= 1
Parabolic Critical Depth
Global Vel Dist=  1 , 1 , 1
Global Log Level= 0
CheckData=True
Encroach Param= -1, 0, 0, 0
BEGIN DESCRIPTION:
Multiple Run
END DESCRIPTION:

--- Spur Branch.f01 (steady flow) ---

Flow Title=Multiple
Number of Profiles=7
Profile Names=10-year,25-year,50-year,1pct_min,100-year,1pct_plu,500-year
River Rch & RM= Spur Branch,Reach-1,26784
     663    1099    1504     997    1990    3970    3436
River Rch & RM= Spur Branch,Reach-1,24523
    1236    2134    2997    2034    4058    8097    7357
River Rch & RM= Spur Branch,Reach-1,21749
    1784    3128    4437    3035    6057   12084   11169
River Rch & RM= Spur Branch,Reach-1,14089
    2284    4043    5771    3969    7918   15799   14756
River Rch & RM= Spur Branch,Reach-1,6380
    2656    4731    6782    4681    9339   18634   17534
River Rch & RM= Spur Branch,Reach-1,998
    4353    7934   11551    8085   16132   32188   31161
Boundary for River Rch & Prof#=Spur Branch,Reach-1,1
Up Type=0
Dn Type=3
Dn Slope=0.005
Boundary for River Rch & Prof#=Spur Branch,Reach-1,2
Up Type=0
Dn Type=3
Dn Slope=0.005
Boundary for River Rch & Prof#=Spur Branch,Reach-1,3
Up Type=0
Dn Type=3
Dn Slope=0.005
Boundary for River Rch & Prof#=Spur Branch,Reach-1,4
Up Type=0
Dn Type=3
Dn Slope=0.005
Boundary for River Rch & Prof#=Spur Branch,Reach-1,5
Up Type=0
Dn Type=3
Dn Slope=0.005
Boundary for River Rch & Prof#=Spur Branch,Reach-1,6
Up Type=0
Dn Type=3
Dn Slope=0.005
Boundary for River Rch & Prof#=Spur Branch,Reach-1,7
Up Type=0
Dn Type=3
Dn Slope=0.005

--- Spur Branch.g01 (geometry) ---

Geom Title=Existing Conditions

River Reach=Spur Branch,Reach-1
Reach XY= 30
      1841475.00     13887025.00      1842317.47     13888675.01
      1841277.07     13891580.86      1841323.24     13892168.87
      1840975.37     13892790.27      1841923.78     13894085.50
      1841967.19     13894428.41      1841526.04     13895135.44
      1841572.99     13895869.32      1841023.42     13896621.17
      1839635.43     13896626.05      1839380.40     13896872.57
      1839477.07     13897769.14      1839825.58     13898450.00
      1839225.75     13899885.68      1839473.91     13900535.54
      1839423.96     13901014.57      1838694.13     13901404.58
      1838769.17     13901977.30      1838175.38     13902390.15
      1838182.80     13902681.20      1838669.17     13903072.70
      1838771.18     13903573.41      1838524.91     13903817.25
      1837795.18     13903624.71      1837330.62     13903780.62
      1837061.77     13904638.67      1836315.00     13904935.65
      1835830.14     13905522.41      1835825.00     13906525.00

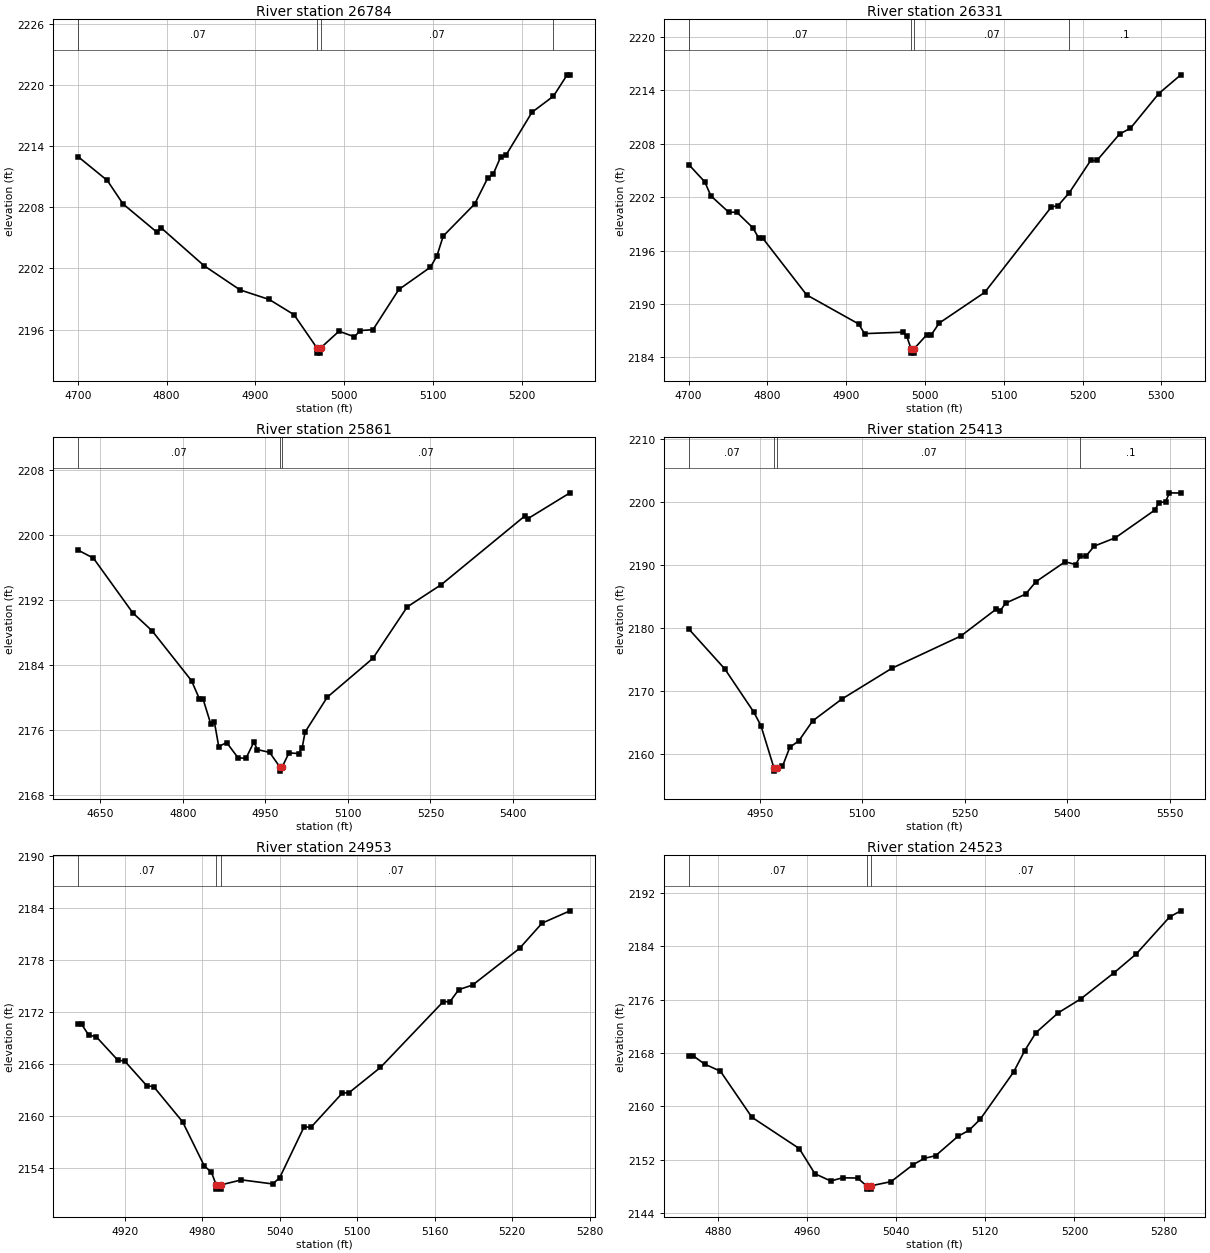
Type RM Length L Ch R = 1,26784,453,453,453
BEGIN DESCRIPTION:
Spur Branch 59.0
END DESCRIPTION:
XS GIS Cut Line= 3
      1841324.98     13887325.00      1841625.00     13887275.00
      1841825.03     13887124.97
#Sta/Elev= 30
  4700.2 2212.96  4733.2 2210.62  4750.9 2208.32  4788.9 2205.56  4794.0 2205.96
  4842.1 2202.27  4882.7 2199.89  4915.6 2198.95  4943.5 2197.46  4969.4 2194.19
  4969.7 2193.69  4973.2 2193.69  4973.4 2194.19  4994.2 2195.84  5011.6 2195.29
  5017.9 2195.90  5032.5 2195.99  5061.6 2199.93  5097.1 2202.11  5104.4 2203.20
  5111.6 2205.17  5147.1 2208.32  5161.6 2210.84  5167.9 2211.24  5176.2 2212.91
  5182.5 2213.13  5211.6 2217.31  5235.8 2218.89  5251.2 2220.98  5254.4 2220.98
#Mann=4,-1,0
  4700.2    0.07       0  4969.4    0.05       0  4973.4    0.07       0
  5235.8     0.1       0
Bank Sta=4969.4,4973.4
Exp/Cntr=0.3,0.1

Type RM Length L Ch R = 1,26331,470,470,470
BEGIN DESCRIPTION:
Spur Branch 58.0
END DESCRIPTION:
XS GIS Cut Line= 3
      1841474.99     13887725.00      1841775.00     13887675.00
      1841974.99     13887425.01
#Sta/Elev= 30
  4700.3 2205.66  4720.6 2203.72  4728.2 2202.16  4751.0 2200.31  4761.1 2200.32
  4781.4 2198.58  4789.0 2197.42  4794.1 2197.40  4849.8 2191.03  4915.7 2187.77
  4923.3 2186.68  4971.5 2186.84  4976.6 2186.45  4982.2 2184.99  4982.4 2184.49
  4985.9 2184.49  4986.2 2184.99  5001.9 2186.52  5007.7 2186.52  5018.1 2187.87
  5075.7 2191.31  5160.5 2200.93  5168.5 2201.03  5183.1 2202.51  5210.2 2206.13
  5218.2 2206.13  5247.0 2209.11  5260.6 2209.74  5296.6 2213.64  5324.6 2215.75
#Mann=4,-1,0
  4700.3    0.07       0  4982.2    0.05       0  4986.2    0.07       0
  5183.1     0.1       0
Bank Sta=4982.2,4986.2
Exp/Cntr=0.3,0.1

Type RM Length L Ch R = 1,25861,448,448,448
BEGIN DESCRIPTION:
Spur Branch 57.0
END DESCRIPTION:
XS GIS Cut Line= 3
      1841725.00     13888375.00      1841975.00     13888075.00
      1842112.40     13887590.42
#Sta/Elev= 30
  4609.5 2198.19  4637.5 2197.20  4709.1 2190.46  4744.2 2188.25  4815.8 2182.11
  4830.1 2179.88  4836.7 2179.87  4851.0 2176.74  4857.5 2176.97  4865.3 2174.00
  4879.6 2174.50  4900.4 2172.62  4914.8 2172.56  4929.1 2174.55  4935.6 2173.63
  4957.7 2173.29  4976.5 2171.48  4976.8 2170.98  4980.5 2171.48  4992.9 2173.22
  5010.4 2173.15  5017.0 2173.88  5022.2 2175.79  5062.4 2180.07  5145.5 2184.87
  5207.9 2191.20  5270.0 2193.95  5421.3 2202.37  5426.5 2202.03  5503.7 2205.24
#Mann=3,-1,0
  4609.5    0.07       0  4976.5    0.05       0  4980.5    0.07       0
Bank Sta=4976.5,4980.5
Exp/Cntr=0.3,0.1

Type RM Length L Ch R = 1,25413,460,460,460
BEGIN DESCRIPTION:
Spur Branch 56.0
END DESCRIPTION:
XS GIS Cut Line= 3
      1842075.00     13888475.00      1842225.00     13888425.00
      1842703.42     13888130.90
#Sta/Elev= 30
  4846.2 2179.78  4898.9 2173.44  4941.1 2166.62  4951.6 2164.47  4970.7 2157.73
  4970.9 2157.23  4974.7 2157.73  4983.2 2158.00  4993.8 2160.99  5007.2 2162.06
  5027.4 2165.21  5070.0 2168.67  5143.4 2173.57  5244.0 2178.67  5296.1 2182.97
  5302.0 2182.72  5309.5 2183.89  5338.7 2185.32  5354.1 2187.31  5396.7 2190.47
  5412.1 2190.02  5418.7 2191.33  5426.9 2191.33  5439.2 2192.95  5470.1 2194.27
  5528.0 2198.68  5533.9 2199.86  5543.5 2199.98  5549.3 2201.41  5565.9 2201.37
#Mann=4,-1,0
  4846.2    0.07       0  4970.7    0.05       0  4974.7    0.07       0
  5418.7     0.1       0
Bank Sta=4970.7,4974.7
Exp/Cntr=0.3,0.1

Type RM Length L Ch R = 1,24953,430,430,430
BEGIN DESCRIPTION:
Spur Branch 55.0
END DESCRIPTION:
XS GIS Cut Line= 3
      1842125.01     13888775.00      1842225.00     13888825.00
      1842475.04     13888925.02
#Sta/Elev= 30
  4883.7 2170.58  4886.5 2170.58  4892.1 2169.32  4897.7 2169.17  4914.4 2166.47
  4920.0 2166.32  4936.8 2163.52  4942.4 2163.37  4964.7 2159.33  4981.5 2154.24
  4987.1 2153.48  4990.7 2152.05  4990.9 2151.55  4994.4 2151.55  4994.7 2152.05
  5010.3 2152.62  5034.5 2152.15  5039.9 2152.86  5058.8 2158.74  5064.2 2158.70
  5088.4 2162.64  5093.8 2162.71  5118.0 2165.61  5166.5 2173.19  5171.9 2173.22
  5178.6 2174.59  5189.4 2175.13  5225.7 2179.36  5243.2 2182.28  5264.8 2183.70
#Mann=3,-1,0
  4883.7    0.07       0  4990.7    0.05       0  4994.7    0.07       0
Bank Sta=4990.7,4994.7
Exp/Cntr=0.3,0.1

Type RM Length L Ch R = 1,24523,444,444,444
BEGIN DESCRIPTION:
Spur Branch 54.0
END DESCRIPTION:
XS GIS Cut Line= 3
      1842025.00     13889125.00      1842125.00     13889225.00
      1842424.98     13889225.00
#Sta/Elev= 30
  4854.0 2167.63  4857.5 2167.63  4868.1 2166.35  4882.3 2165.28  4910.6 2158.37
  4953.0 2153.69  4967.1 2149.91  4981.3 2148.82  4991.9 2149.30  5005.4 2149.26
  5013.4 2148.10  5013.7 2147.60  5017.2 2147.60  5017.4 2148.10  5035.4 2148.72
  5055.4 2151.29  5065.4 2152.22  5075.4 2152.61  5095.4 2155.51  5105.4 2156.42
  5115.4 2158.07  5145.4 2165.16  5155.4 2168.37  5165.4 2171.05  5185.4 2174.03
  5205.4 2176.09  5235.4 2180.02  5255.4 2182.85  5285.4 2188.41  5295.4 2189.32
#Mann=3,-1,0
  4854.0    0.07       0  5013.4    0.05       0  5017.4    0.07       0
Bank Sta=5013.4,5017.4
Exp/Cntr=0.3,0.1

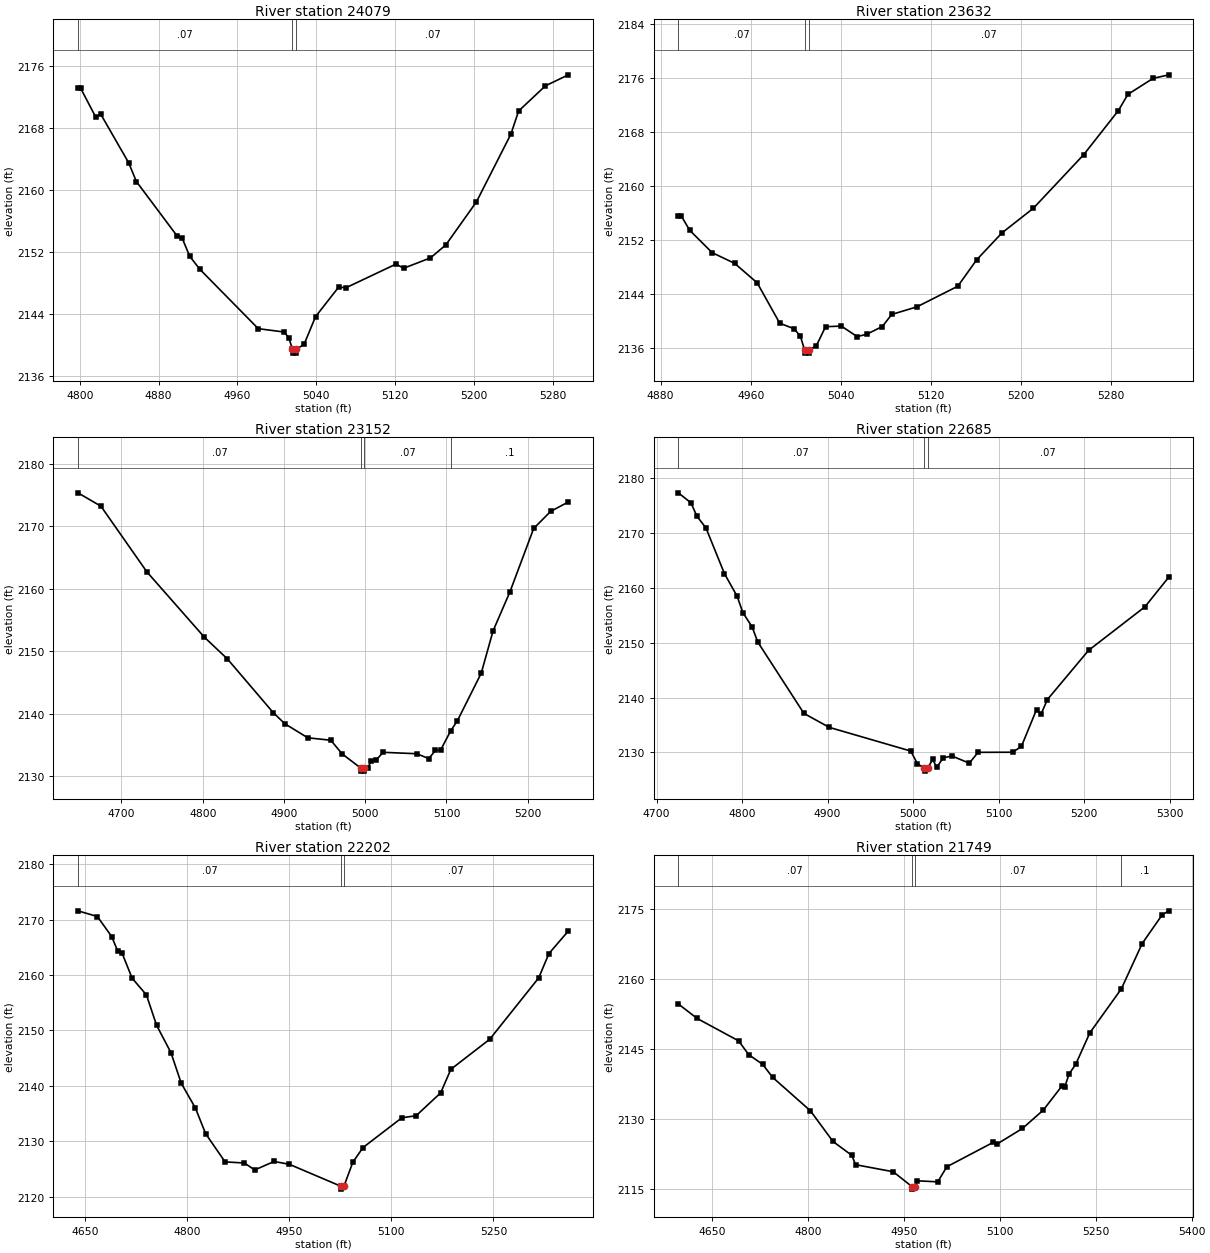
Type RM Length L Ch R = 1,24079,447,447,447
BEGIN DESCRIPTION:
Spur Branch 53.0
END DESCRIPTION:
XS GIS Cut Line= 3
      1841875.01     13889575.00      1842075.00     13889625.00
      1842225.00     13889875.01
#Sta/Elev= 30
  4798.2 2173.13  4800.8 2173.13  4816.2 2169.39  4821.4 2169.74  4849.7 2163.49
  4857.5 2161.08  4898.7 2154.09  4903.8 2153.84  4911.6 2151.46  4921.9 2149.78
  4981.2 2142.13  5007.3 2141.70  5012.1 2140.99  5015.9 2139.48  5016.2 2138.98
  5019.7 2138.98  5019.9 2139.48  5027.7 2140.11  5039.3 2143.67  5062.7 2147.47
  5070.4 2147.41  5121.0 2150.45  5128.7 2149.91  5155.9 2151.24  5171.5 2152.91
  5202.6 2158.46  5237.6 2167.19  5245.4 2170.16  5272.6 2173.40  5295.9 2174.82
#Mann=3,-1,0
  4798.2    0.07       0  5015.9    0.05       0  5019.9    0.07       0
Bank Sta=5015.9,5019.9
Exp/Cntr=0.3,0.1

Type RM Length L Ch R = 1,23632,480,480,480
BEGIN DESCRIPTION:
Spur Branch 52.0
END DESCRIPTION:
XS GIS Cut Line= 3
      1841725.00     13889975.00      1841825.00     13889975.00
      1842124.99     13890125.00
#Sta/Elev= 30
  4895.7 2155.65  4898.2 2155.65  4905.7 2153.50  4925.7 2150.18  4945.7 2148.59
  4965.7 2145.71  4985.7 2139.74  4998.5 2138.91  5004.1 2137.79  5007.7 2135.81
  5007.9 2135.31  5011.4 2135.31  5011.7 2135.81  5018.1 2136.36  5026.4 2139.22
  5040.4 2139.31  5054.4 2137.76  5062.8 2138.09  5076.8 2139.25  5085.1 2141.03
  5107.5 2142.16  5143.8 2145.21  5160.6 2149.13  5183.0 2153.10  5210.9 2156.75
  5255.6 2164.68  5286.4 2171.21  5294.8 2173.60  5317.1 2175.96  5331.1 2176.49
#Mann=3,-1,0
  4895.7    0.07       0  5007.7    0.05       0  5011.7    0.07       0
Bank Sta=5007.7,5011.7
Exp/Cntr=0.3,0.1

Type RM Length L Ch R = 1,23152,467,467,467
BEGIN DESCRIPTION:
Spur Branch 51.0
END DESCRIPTION:
XS GIS Cut Line= 3
      1841474.98     13890174.98      1841725.00     13890425.00
      1841925.01     13890575.01
#Sta/Elev= 30
  4646.4 2175.31  4674.7 2173.17  4731.3 2162.66  4802.0 2152.22  4830.3 2148.75
  4886.8 2140.15  4901.0 2138.38  4929.3 2136.13  4957.6 2135.74  4971.7 2133.54
  4994.4 2131.30  4994.7 2130.80  4998.2 2130.80  4998.4 2131.30  5003.1 2131.30
  5007.3 2132.40  5013.5 2132.57  5021.9 2133.81  5063.5 2133.58  5078.1 2132.81
  5086.4 2134.10  5092.7 2134.15  5105.2 2137.25  5113.5 2138.88  5142.7 2146.45
  5157.3 2153.22  5178.1 2159.48  5207.3 2169.61  5228.1 2172.33  5250.0 2173.85
#Mann=4,-1,0
  4646.4    0.07       0  4994.4    0.05       0  4998.4    0.07       0
  5105.2     0.1       0
Bank Sta=4994.4,4998.4
Exp/Cntr=0.3,0.1

Type RM Length L Ch R = 1,22685,483,483,483
BEGIN DESCRIPTION:
Spur Branch 50.0
END DESCRIPTION:
XS GIS Cut Line= 3
      1841274.99     13890724.99      1841525.00     13890825.00
      1841824.99     13890775.00
#Sta/Elev= 30
  4725.5 2177.37  4740.3 2175.54  4747.1 2173.13  4757.8 2170.95  4779.4 2162.62
  4794.2 2158.50  4800.9 2155.51  4811.7 2152.91  4818.4 2150.13  4872.3 2137.11
  4901.9 2134.56  4997.3 2130.23  5004.9 2127.95  5013.0 2127.07  5013.3 2126.57
  5017.0 2127.07  5022.7 2128.70  5027.7 2127.29  5035.3 2129.02  5045.5 2129.32
  5065.7 2128.02  5075.9 2130.00  5116.4 2130.02  5126.6 2131.08  5144.3 2137.81
  5149.4 2136.92  5157.0 2139.64  5205.1 2148.61  5271.0 2156.56  5298.9 2161.98
#Mann=3,-1,0
  4725.5    0.07       0  5013.0    0.05       0  5017.0    0.07       0
Bank Sta=5013,5017
Exp/Cntr=0.3,0.1

Type RM Length L Ch R = 1,22202,453,453,453
BEGIN DESCRIPTION:
Spur Branch 49.0
END DESCRIPTION:
XS GIS Cut Line= 3
      1841124.96     13891074.98      1841425.00     13891275.00
      1841725.04     13891475.03
#Sta/Elev= 30
  4639.0 2171.62  4667.6 2170.59  4688.6 2166.98  4697.6 2164.32  4703.6 2164.06
  4718.7 2159.45  4739.7 2156.43  4754.7 2150.93  4775.8 2145.99  4790.8 2140.50
  4811.8 2135.97  4826.8 2131.35  4855.4 2126.26  4883.9 2126.06  4898.9 2124.80
  4927.5 2126.34  4950.0 2125.82  5026.1 2121.84  5026.4 2121.34  5030.1 2121.84
  5043.2 2126.19  5058.2 2128.85  5115.3 2134.23  5136.3 2134.60  5172.4 2138.73
  5187.4 2142.99  5244.5 2148.41  5316.6 2159.51  5331.6 2163.90  5360.2 2167.98
#Mann=3,-1,0
  4639.0    0.07       0  5026.1    0.05       0  5030.1    0.07       0
Bank Sta=5026.1,5030.1
Exp/Cntr=0.3,0.1

Type RM Length L Ch R = 1,21749,459,459,459
BEGIN DESCRIPTION:
Spur Branch 48.0
END DESCRIPTION:
XS GIS Cut Line= 3
      1841075.01     13891325.02      1841275.00     13891675.00
      1841625.01     13891775.00
#Sta/Elev= 30
  4597.1 2154.58  4626.6 2151.48  4691.4 2146.69  4707.2 2143.73  4728.8 2141.69
  4744.6 2138.88  4803.7 2131.72  4838.9 2125.17  4868.5 2122.18  4874.2 2120.19
  4933.2 2118.68  4962.9 2115.46  4963.1 2114.96  4967.0 2115.46  4970.7 2116.74
  5002.8 2116.52  5017.1 2119.75  5089.9 2124.99  5095.1 2124.57  5135.4 2127.95
  5167.9 2131.87  5196.5 2136.93  5201.7 2136.89  5208.2 2139.60  5218.6 2141.66
  5240.7 2148.40  5290.0 2157.82  5322.6 2167.52  5353.8 2173.65  5364.2 2174.52
#Mann=4,-1,0
  4597.1    0.07       0  4962.9    0.05       0  4967.0    0.07       0
  5290.0     0.1       0
Bank Sta=4962.9,4967
Exp/Cntr=0.3,0.1

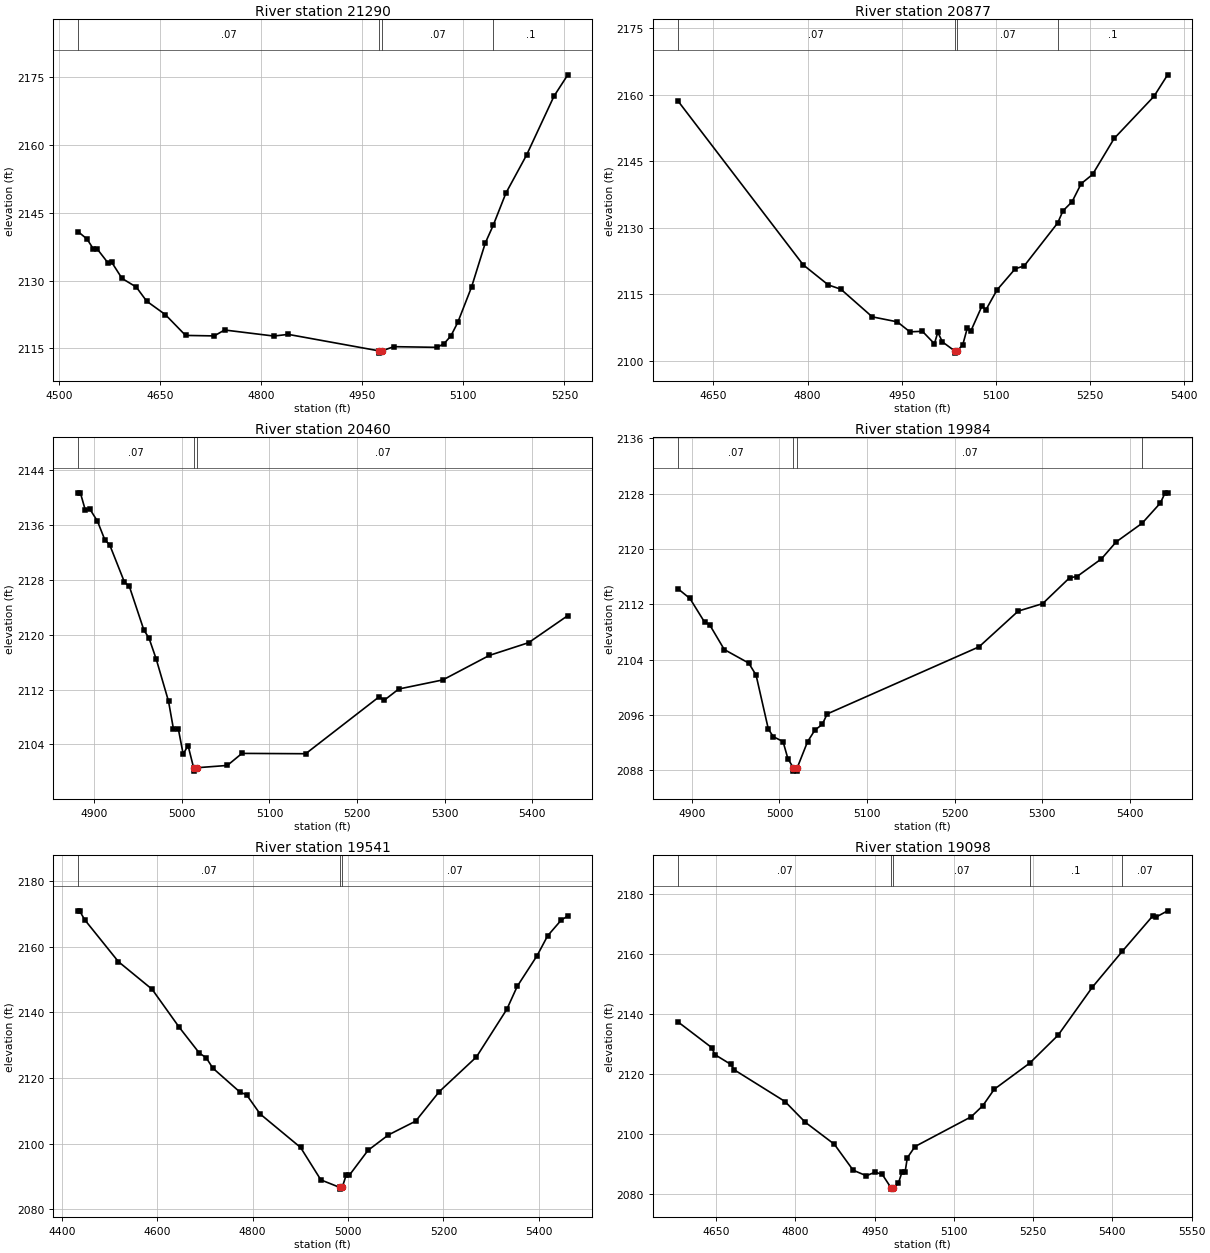
Type RM Length L Ch R = 1,21290,413,413,413
BEGIN DESCRIPTION:
Spur Branch 47.0
END DESCRIPTION:
XS GIS Cut Line= 3
      1840875.04     13892324.97      1841275.00     13892075.00
      1841525.00     13892125.00
#Sta/Elev= 30
  4528.4 2140.85  4541.9 2139.18  4551.3 2137.00  4557.2 2136.95  4572.6 2133.98
  4578.5 2134.05  4593.8 2130.47  4615.0 2128.55  4630.4 2125.43  4658.1 2122.45
  4688.1 2117.85  4730.6 2117.74  4745.9 2119.05  4819.0 2117.71  4840.3 2118.08
  4975.0 2114.43  4975.3 2113.93  4979.1 2114.43  4997.1 2115.36  5061.2 2115.21
  5071.4 2116.02  5081.6 2117.74  5091.8 2120.73  5112.2 2128.54  5132.6 2138.30
  5144.3 2142.20  5163.2 2149.35  5193.8 2157.76  5234.6 2170.83  5255.0 2175.53
#Mann=4,-1,0
  4528.4    0.07       0  4975.0    0.05       0  4979.1    0.07       0
  5144.3     0.1       0
Bank Sta=4975,4979.1
Exp/Cntr=0.3,0.1

Type RM Length L Ch R = 1,20877,417,417,417
BEGIN DESCRIPTION:
Spur Branch 46.0
END DESCRIPTION:
XS GIS Cut Line= 3
      1840775.00     13892425.00      1841175.00     13892425.00
      1841525.01     13892275.00
#Sta/Elev= 30
  4593.0 2158.67  4793.0 2121.65  4833.0 2117.12  4853.0 2116.16  4903.0 2109.93
  4943.0 2108.80  4963.0 2106.55  4983.0 2106.67  5002.1 2103.86  5007.5 2106.45
  5014.8 2104.29  5034.4 2102.25  5034.7 2101.75  5038.7 2102.25  5047.4 2103.68
  5054.7 2107.49  5060.1 2106.71  5078.2 2112.47  5083.7 2111.39  5101.8 2115.98
  5130.8 2120.75  5145.3 2121.43  5198.5 2131.08  5207.0 2133.82  5221.5 2135.88
  5236.0 2139.95  5254.1 2142.02  5288.6 2150.15  5352.0 2159.63  5373.8 2164.49
#Mann=4,-1,0
  4593.0    0.07       0  5034.4    0.05       0  5038.7    0.07       0
  5198.5     0.1       0
Bank Sta=5034.4,5038.7
Exp/Cntr=0.3,0.1

Type RM Length L Ch R = 1,20460,476,476,476
BEGIN DESCRIPTION:
Spur Branch 45.0
END DESCRIPTION:
XS GIS Cut Line= 3
      1840875.04     13892725.02      1840975.00     13892775.00
      1841375.02     13892574.99
#Sta/Elev= 30
  4881.4 2140.73  4884.2 2140.73  4889.7 2138.27  4895.3 2138.30  4903.7 2136.59
  4912.1 2133.87  4917.7 2133.12  4934.5 2127.69  4940.1 2127.06  4956.8 2120.64
  4962.4 2119.56  4970.8 2116.43  4984.8 2110.29  4990.4 2106.25  4996.0 2106.25
  5001.5 2102.58  5007.1 2103.82  5013.4 2100.59  5013.7 2100.09  5017.7 2100.59
  5051.9 2100.92  5068.6 2102.68  5141.3 2102.63  5225.2 2110.95  5230.7 2110.42
  5247.5 2112.08  5297.8 2113.41  5350.9 2116.99  5395.7 2118.85  5440.4 2122.80
#Mann=3,-1,0
  4881.4    0.07       0  5013.4    0.05       0  5017.7    0.07       0
Bank Sta=5013.4,5017.7
Exp/Cntr=0.3,0.1

Type RM Length L Ch R = 1,19984,443,443,443
BEGIN DESCRIPTION:
Spur Branch 44.0
END DESCRIPTION:
XS GIS Cut Line= 3
      1841125.01     13893274.97      1841175.00     13893175.00
      1841575.01     13892974.99
#Sta/Elev= 30
  4883.9 2114.27  4897.8 2112.84  4914.6 2109.40  4920.2 2109.06  4937.0 2105.45
  4964.9 2103.49  4973.3 2101.75  4987.3 2093.94  4992.9 2092.85  5004.1 2092.13
  5009.6 2089.66  5015.7 2088.36  5016.0 2087.86  5020.0 2087.86  5020.3 2088.36
  5032.0 2092.10  5040.4 2093.80  5048.8 2094.61  5054.4 2096.13  5227.7 2105.84
  5272.4 2111.01  5300.3 2112.09  5331.1 2115.84  5339.5 2116.01  5367.4 2118.57
  5384.2 2121.02  5413.8 2123.72  5434.5 2126.63  5440.1 2128.12  5442.9 2128.12
#Mann=4,-1,0
  4883.9    0.07       0  5015.7    0.05       0  5020.3    0.07       0
  5413.8     0.1       0
Bank Sta=5015.7,5020.3
Exp/Cntr=0.3,0.1

Type RM Length L Ch R = 1,19541,443,443,443
BEGIN DESCRIPTION:
Spur Branch 43.0
END DESCRIPTION:
XS GIS Cut Line= 3
      1841125.03     13893824.97      1841525.00     13893425.00
      1841874.99     13893125.01
#Sta/Elev= 30
  4433.9 2170.94  4437.4 2170.94  4448.0 2168.24  4518.7 2155.45  4589.4 2147.02
  4646.0 2135.48  4688.4 2127.57  4702.6 2126.17  4716.7 2122.98  4773.3 2115.70
  4787.4 2114.85  4815.7 2109.02  4900.5 2098.80  4943.0 2088.92  4983.0 2086.60
  4983.4 2086.10  4987.7 2086.60  4996.0 2090.36  5002.8 2090.36  5041.8 2097.92
  5084.6 2102.63  5141.7 2106.83  5191.1 2115.81  5269.0 2126.39  5332.7 2140.92
  5354.6 2147.94  5396.3 2157.31  5418.3 2163.34  5446.8 2168.13  5460.5 2169.36
#Mann=3,-1,0
  4433.9    0.07       0  4983.0    0.05       0  4987.7    0.07       0
Bank Sta=4983,4987.7
Exp/Cntr=0.3,0.1

Type RM Length L Ch R = 1,19098,451,451,451
BEGIN DESCRIPTION:
Spur Branch 42.0
END DESCRIPTION:
XS GIS Cut Line= 3
      1841374.96     13893925.02      1841775.00     13893775.00
      1842174.96     13893475.03
#Sta/Elev= 30
  4577.3 2137.39  4641.4 2128.78  4647.7 2126.40  4677.9 2123.15  4684.1 2121.36
  4780.3 2110.78  4818.5 2103.89  4873.7 2096.53  4909.3 2087.88  4934.2 2086.03
  4951.1 2087.24  4964.5 2086.45  4980.8 2082.07  4981.2 2081.57  4985.5 2082.07
  4994.8 2083.46  5001.9 2087.35  5007.7 2087.35  5011.8 2092.00  5026.4 2095.77
  5132.7 2105.69  5154.5 2109.34  5176.4 2114.87  5243.4 2123.57  5297.3 2132.91
  5361.8 2148.84  5418.9 2160.90  5476.4 2172.66  5482.7 2172.28  5504.5 2174.35
#Mann=5,-1,0
  4577.3    0.07       0  4980.8    0.05       0  4985.5    0.07       0
  5243.4     0.1       0  5418.9    0.07       0
Bank Sta=4980.8,4985.5
Exp/Cntr=0.3,0.1

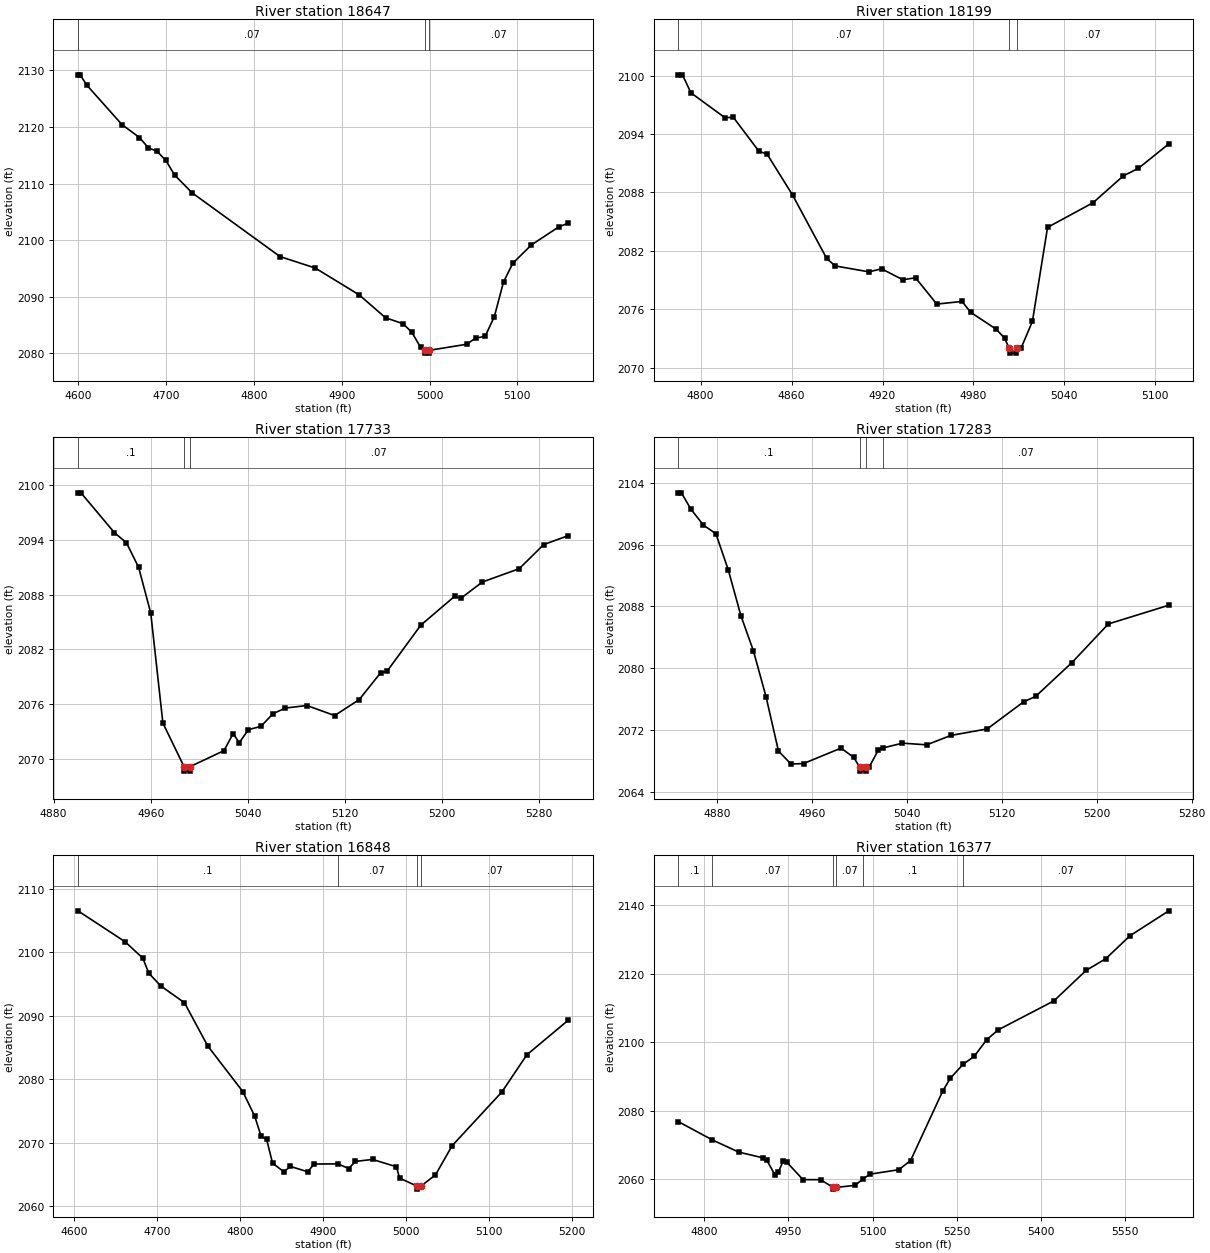
Type RM Length L Ch R = 1,18647,448,448,448
BEGIN DESCRIPTION:
Spur Branch 41.0
END DESCRIPTION:
XS GIS Cut Line= 3
      1841524.99     13894175.00      1841925.00     13894175.00
      1842074.98     13894125.01
#Sta/Elev= 30
  4599.9 2129.21  4602.4 2129.21  4609.9 2127.40  4649.9 2120.43  4669.9 2118.13
  4679.9 2116.32  4689.9 2115.70  4699.9 2114.09  4709.9 2111.50  4729.9 2108.35
  4829.9 2097.09  4869.9 2095.07  4919.9 2090.33  4949.9 2086.28  4969.9 2085.23
  4979.9 2083.70  4989.9 2081.03  4995.1 2080.53  4995.4 2080.03  4999.5 2080.03
  4999.8 2080.53  5042.1 2081.59  5052.6 2082.70  5063.2 2082.98  5073.7 2086.46
  5084.2 2092.61  5094.8 2095.92  5115.9 2099.15  5147.5 2102.38  5158.0 2102.99
#Mann=3,-1,0
  4599.9    0.07       0  4995.1    0.05       0  4999.8    0.07       0
Bank Sta=4995.1,4999.8
Exp/Cntr=0.3,0.1

Type RM Length L Ch R = 1,18199,466,466,466
BEGIN DESCRIPTION:
Spur Branch 40.0
END DESCRIPTION:
XS GIS Cut Line= 3
      1841675.04     13894475.02      1841875.00     13894575.00
      1841975.04     13894575.00
#Sta/Elev= 30
  4785.3 2100.08  4788.0 2100.08  4793.6 2098.23  4816.0 2095.68  4821.6 2095.71
  4838.4 2092.24  4843.9 2091.92  4860.7 2087.72  4883.1 2081.23  4888.7 2080.45
  4911.0 2079.84  4919.4 2080.15  4933.4 2079.03  4941.8 2079.23  4955.8 2076.53
  4972.5 2076.80  4978.1 2075.69  4994.9 2073.96  5000.5 2073.04  5003.6 2071.99
  5003.9 2071.49  5008.2 2071.49  5008.6 2071.99  5011.4 2071.99  5018.9 2074.75
  5028.9 2084.41  5058.9 2086.94  5078.9 2089.70  5088.9 2090.48  5108.9 2092.99
#Mann=3,-1,0
  4785.3    0.07       0  5003.6    0.05       0  5008.6    0.07       0
Bank Sta=5003.6,5008.6
Exp/Cntr=0.3,0.1

Type RM Length L Ch R = 1,17733,450,450,450
BEGIN DESCRIPTION:
Spur Branch 39.0
END DESCRIPTION:
XS GIS Cut Line= 3
      1841525.02     13894925.00      1841625.00     13894925.00
      1841924.98     13894975.00
#Sta/Elev= 30
  4900.0 2099.14  4902.5 2099.14  4930.0 2094.79  4940.0 2093.67  4950.0 2090.99
  4960.0 2085.98  4970.0 2073.95  4987.4 2069.19  4987.8 2068.69  4992.1 2068.69
  4992.5 2069.19  5020.3 2070.93  5027.9 2072.80  5032.9 2071.80  5040.5 2073.23
  5050.7 2073.58  5060.8 2074.98  5070.9 2075.59  5088.7 2075.87  5111.5 2074.77
  5131.8 2076.52  5149.5 2079.47  5154.6 2079.60  5182.5 2084.66  5210.3 2087.81
  5215.4 2087.59  5233.2 2089.38  5263.6 2090.84  5283.8 2093.48  5304.1 2094.46
#Mann=3,-1,0
  4900.0     0.1       0  4987.4    0.05       0  4992.5    0.07       0
Bank Sta=4987.4,4992.5
Exp/Cntr=0.3,0.1

Type RM Length L Ch R = 1,17283,435,435,435
BEGIN DESCRIPTION:
Spur Branch 38.0
END DESCRIPTION:
XS GIS Cut Line= 3
      1841425.02     13895275.01      1841575.00     13895325.00
      1841824.96     13895374.99
#Sta/Elev= 30
  4847.7 2102.70  4850.3 2102.70  4858.2 2100.60  4868.8 2098.52  4879.3 2097.41
  4889.8 2092.70  4900.4 2086.79  4910.9 2082.26  4921.5 2076.34  4932.0 2069.30
  4942.5 2067.62  4953.1 2067.68  4984.7 2069.68  4995.3 2068.48  5000.5 2067.20
  5000.9 2066.70  5005.4 2066.70  5005.8 2067.20  5008.3 2067.20  5016.0 2069.41
  5020.1 2069.70  5036.4 2070.32  5056.8 2070.10  5077.2 2071.32  5107.8 2072.16
  5138.4 2075.66  5148.6 2076.37  5179.2 2080.75  5209.8 2085.74  5260.7 2088.16
#Mann=4,-1,0
  4847.7     0.1       0  5000.5    0.05       0  5005.8     0.1       0
  5020.1    0.07       0
Bank Sta=5000.5,5005.8
Exp/Cntr=0.3,0.1

Type RM Length L Ch R = 1,16848,471,471,471
BEGIN DESCRIPTION:
Spur Branch 37.0
END DESCRIPTION:
XS GIS Cut Line= 3
      1841275.00     13895475.00      1841575.00     13895725.00
      1841774.98     13895725.00
#Sta/Elev= 30
  4604.9 2106.57  4661.5 2101.71  4683.0 2099.11  4690.2 2096.74  4704.5 2094.74
  4733.1 2092.09  4761.1 2085.28  4803.4 2078.07  4817.7 2074.20  4825.5 2071.01
  4832.1 2070.54  4839.2 2066.79  4852.9 2065.42  4860.7 2066.27  4881.5 2065.43
  4889.3 2066.65  4917.9 2066.67  4931.0 2065.94  4938.8 2067.06  4959.6 2067.37
  4988.3 2066.22  4992.2 2064.43  5012.7 2063.19  5013.2 2062.69  5018.1 2063.19
  5035.4 2064.93  5055.4 2069.53  5115.4 2078.02  5145.4 2083.87  5195.4 2089.34
#Mann=4,-1,0
  4604.9     0.1       0  4917.9    0.07       0  5012.7    0.05       0
  5018.1    0.07       0
Bank Sta=5012.7,5018.1
Exp/Cntr=0.3,0.1

Type RM Length L Ch R = 1,16377,467,467,467
BEGIN DESCRIPTION:
Spur Branch 36.0
END DESCRIPTION:
XS GIS Cut Line= 3
      1841224.96     13895974.97      1841425.00     13896125.00
      1841823.31     13896604.24
#Sta/Elev= 30
  4754.3 2076.80  4814.4 2071.50  4861.6 2067.91  4904.3 2066.25  4911.6 2065.57
  4926.2 2061.29  4932.5 2062.16  4940.8 2065.23  4947.1 2065.01  4976.2 2059.86
  5007.6 2059.85  5029.6 2057.59  5030.0 2057.09  5035.1 2057.59  5068.8 2058.19
  5083.5 2060.14  5096.1 2061.48  5146.9 2062.76  5167.8 2065.45  5225.0 2085.75
  5238.4 2089.45  5261.3 2093.57  5281.0 2095.85  5303.2 2100.73  5324.0 2103.63
  5422.9 2112.07  5480.2 2120.97  5515.4 2124.40  5558.4 2131.10  5627.5 2138.38
#Mann=6,-1,0
  4754.3     0.1       0  4814.4    0.07       0  5029.6    0.05       0
  5035.1    0.07       0  5083.5     0.1       0  5261.3    0.07       0
Bank Sta=5029.6,5035.1
Exp/Cntr=0.3,0.1

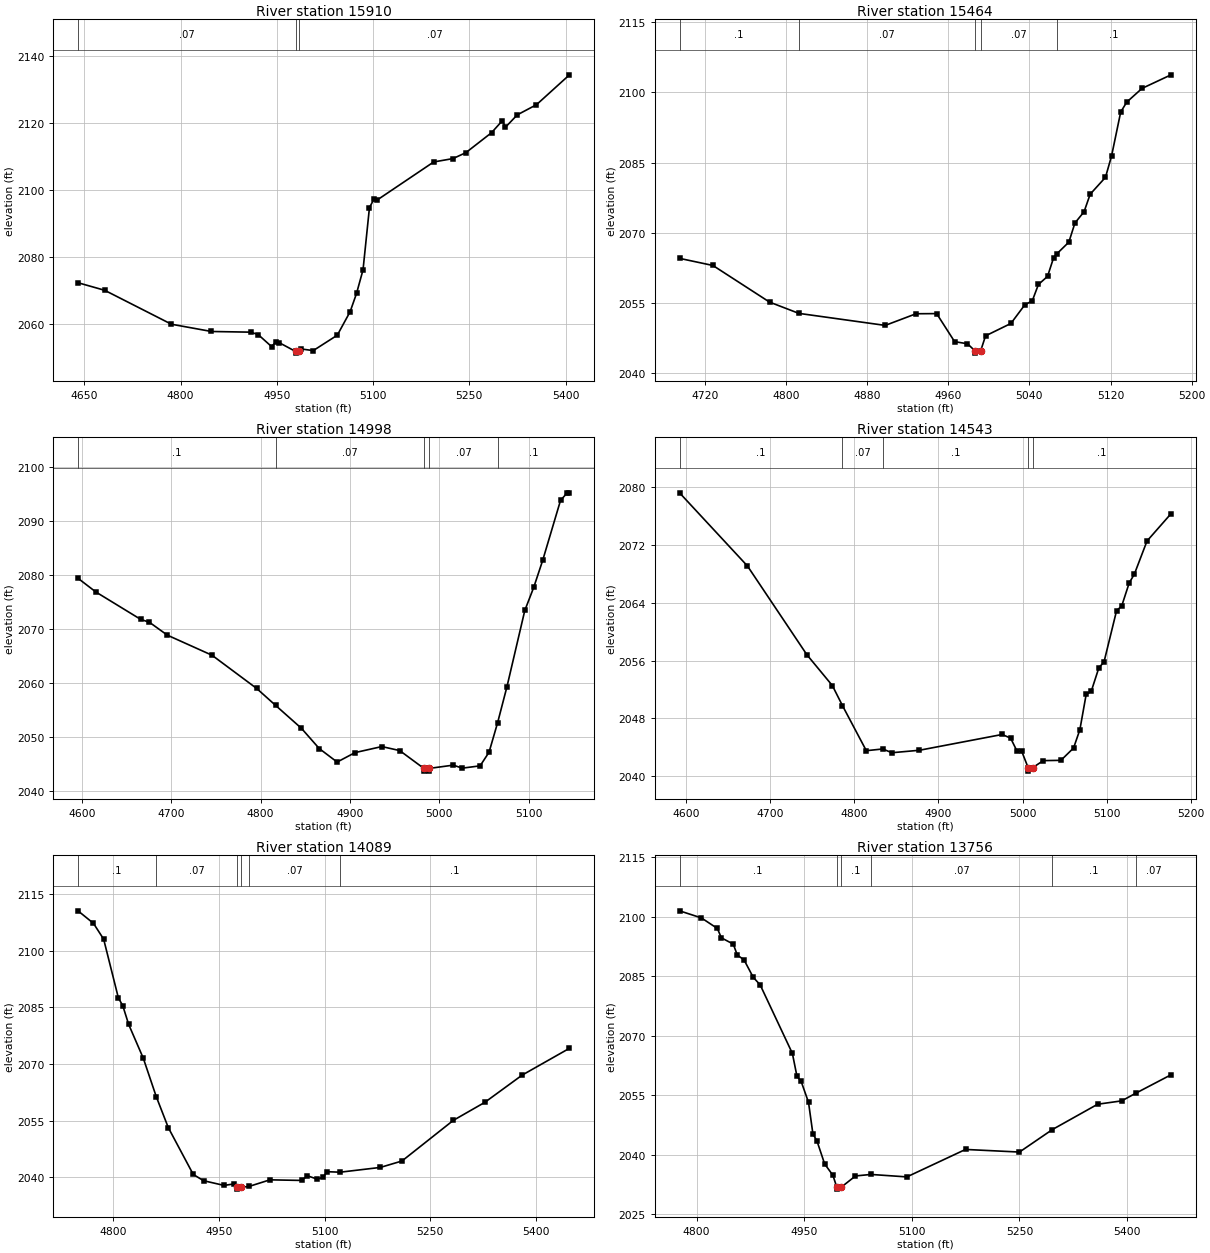
Type RM Length L Ch R = 1,15910,446,446,446
BEGIN DESCRIPTION:
Spur Branch 35.0
END DESCRIPTION:
XS GIS Cut Line= 3
      1841124.99     13896174.96      1841225.00     13896525.00
      1841245.17     13896926.34
#Sta/Elev= 30
  4640.1 2072.42  4681.7 2070.17  4785.7 2060.07  4848.1 2057.91  4909.2 2057.71
  4920.9 2056.99  4941.7 2053.43  4948.2 2054.72  4953.4 2054.61  4979.2 2051.97
  4979.6 2051.47  4984.9 2051.97  4987.2 2052.73  5006.7 2052.22  5044.2 2056.81
  5064.2 2063.81  5074.2 2069.25  5084.3 2076.27  5094.3 2094.77  5101.5 2097.37
  5106.5 2097.06  5194.4 2108.36  5224.4 2109.36  5244.5 2111.12  5284.5 2117.06
  5301.3 2120.62  5306.3 2118.70  5324.6 2122.37  5354.6 2125.40  5406.0 2134.29
#Mann=3,-1,0
  4640.1    0.07       0  4979.2    0.05       0  4984.9    0.07       0
Bank Sta=4979.2,4984.9
Exp/Cntr=0.3,0.1

Type RM Length L Ch R = 1,15464,466,466,466
BEGIN DESCRIPTION:
Spur Branch 34.0
END DESCRIPTION:
XS GIS Cut Line= 3
      1840874.99     13896375.05      1840825.00     13896675.00
      1840975.03     13896775.02
#Sta/Elev= 30
  4695.2 2064.54  4728.1 2063.02  4783.9 2055.20  4812.8 2052.79  4897.9 2050.22
  4928.3 2052.71  4948.6 2052.74  4966.3 2046.75  4979.0 2046.30  4986.3 2044.80
  4986.8 2044.30  4992.0 2044.80  4996.8 2047.99  5021.8 2050.64  5035.3 2054.56
  5042.9 2055.50  5048.9 2058.96  5057.9 2060.70  5063.9 2064.70  5066.8 2065.45
  5078.9 2068.01  5084.9 2072.10  5093.9 2074.50  5099.9 2078.24  5115.0 2081.85
  5121.0 2086.42  5130.0 2095.80  5136.0 2097.92  5151.0 2100.84  5179.6 2103.74
#Mann=5,-1,0
  4695.2     0.1       0  4812.8    0.07       0  4986.3    0.05       0
  4992.0    0.07       0  5066.8     0.1       0
Bank Sta=4986.3,4992
Exp/Cntr=0.3,0.1

Type RM Length L Ch R = 1,14998,455,455,455
BEGIN DESCRIPTION:
Spur Branch 33.0
END DESCRIPTION:
XS GIS Cut Line= 3
      1840375.00     13896224.99      1840375.00     13896625.00
      1840375.00     13896774.99
#Sta/Elev= 30
  4595.7 2079.43  4615.7 2076.89  4665.7 2071.83  4675.7 2071.27  4695.7 2068.89
  4745.7 2065.17  4795.7 2059.01  4816.9 2055.87  4845.7 2051.64  4865.7 2047.88
  4885.7 2045.38  4905.7 2047.13  4935.7 2048.25  4955.7 2047.51  4982.8 2044.20
  4983.3 2043.70  4988.1 2043.70  4988.6 2044.20  5015.7 2044.81  5025.7 2044.25
  5045.7 2044.68  5055.7 2047.20  5065.3 2052.68  5075.7 2059.31  5095.7 2073.46
  5105.7 2077.74  5115.7 2082.73  5135.7 2093.86  5143.2 2095.26  5145.7 2095.26
#Mann=5,-1,0
  4595.7     0.1       0  4816.9    0.07       0  4982.8    0.05       0
  4988.6    0.07       0  5065.3     0.1       0
Bank Sta=4982.8,4988.6
Exp/Cntr=0.3,0.1

Type RM Length L Ch R = 1,14543,454,454,454
BEGIN DESCRIPTION:
Spur Branch 32.0
END DESCRIPTION:
XS GIS Cut Line= 3
      1840025.00     13896225.00      1839975.00     13896625.00
      1840075.00     13896775.00
#Sta/Elev= 30
  4592.7 2079.15  4673.3 2069.05  4743.9 2056.79  4774.1 2052.54  4786.1 2049.77
  4814.4 2043.55  4833.9 2043.79  4844.7 2043.27  4877.4 2043.61  4975.7 2045.79
  4985.7 2045.28  4993.3 2043.49  4998.8 2043.49  5006.4 2041.23  5006.9 2040.73
  5012.2 2041.23  5024.4 2042.18  5045.4 2042.22  5060.4 2043.92  5067.9 2046.45
  5075.4 2051.34  5081.4 2051.75  5090.5 2055.02  5096.5 2055.78  5111.5 2062.90
  5117.5 2063.51  5126.5 2066.73  5132.5 2067.90  5147.6 2072.50  5176.1 2076.27
#Mann=5,-1,0
  4592.7     0.1       0  4786.1    0.07       0  4833.9     0.1       0
  5006.4    0.05       0  5012.2     0.1       0
Bank Sta=5006.4,5012.2
Exp/Cntr=0.3,0.1

Type RM Length L Ch R = 1,14089,333,333,333
BEGIN DESCRIPTION:
Spur Branch 31.0
END DESCRIPTION:
XS GIS Cut Line= 3
      1839375.01     13896525.01      1839575.00     13896675.00
      1839975.00     13896875.00
#Sta/Elev= 30
  4750.3 2110.50  4772.2 2107.20  4786.7 2103.01  4807.6 2087.46  4813.8 2085.42
  4822.2 2080.45  4843.0 2071.48  4861.3 2061.37  4878.4 2053.16  4913.8 2040.78
  4928.4 2039.12  4957.6 2037.87  4972.2 2038.29  4975.3 2037.39  4975.8 2036.89
  4981.6 2037.39  4992.9 2037.60  5022.6 2039.35  5067.4 2039.19  5075.8 2040.42
  5089.7 2039.53  5098.1 2040.06  5103.7 2041.50  5122.2 2041.37  5179.2 2042.63
  5209.9 2044.33  5282.6 2055.06  5327.3 2059.83  5380.4 2067.05  5447.5 2074.14
#Mann=6,-1,0
  4750.3     0.1       0  4861.3    0.07       0  4975.3    0.05       0
  4981.6   0.035       0  4992.9    0.07       0  5122.2     0.1       0
Bank Sta=4975.3,4981.6
Exp/Cntr=0.3,0.1

Type RM Length L Ch R = 1,13756,596,596,596
BEGIN DESCRIPTION:
Spur Branch 30.0
END DESCRIPTION:
XS GIS Cut Line= 3
      1839174.98     13896824.99      1839375.77     13896927.83
      1839824.99     13897025.00
#Sta/Elev= 30
  4776.2 2101.51  4806.7 2099.72  4828.9 2097.07  4834.5 2094.71  4851.1 2093.12
  4856.7 2090.37  4866.1 2089.15  4878.9 2084.77  4888.6 2082.85  4933.5 2065.59
  4939.9 2059.81  4945.6 2058.60  4956.0 2053.26  4962.1 2045.34  4967.8 2043.51
  4978.5 2037.73  4990.0 2034.88  4995.4 2031.89  4995.9 2031.39  5001.7 2031.89
  5021.5 2034.71  5043.1 2035.09  5093.1 2034.47  5174.9 2041.39  5250.1 2040.73
  5296.0 2046.40  5359.1 2052.78  5392.7 2053.63  5412.4 2055.57  5461.4 2060.20
#Mann=6,-1,0
  4776.2     0.1       0  4995.4    0.05       0  5001.7     0.1       0
  5043.1    0.07       0  5296.0     0.1       0  5412.4    0.07       0
Bank Sta=4995.4,5001.7
Exp/Cntr=0.3,0.1