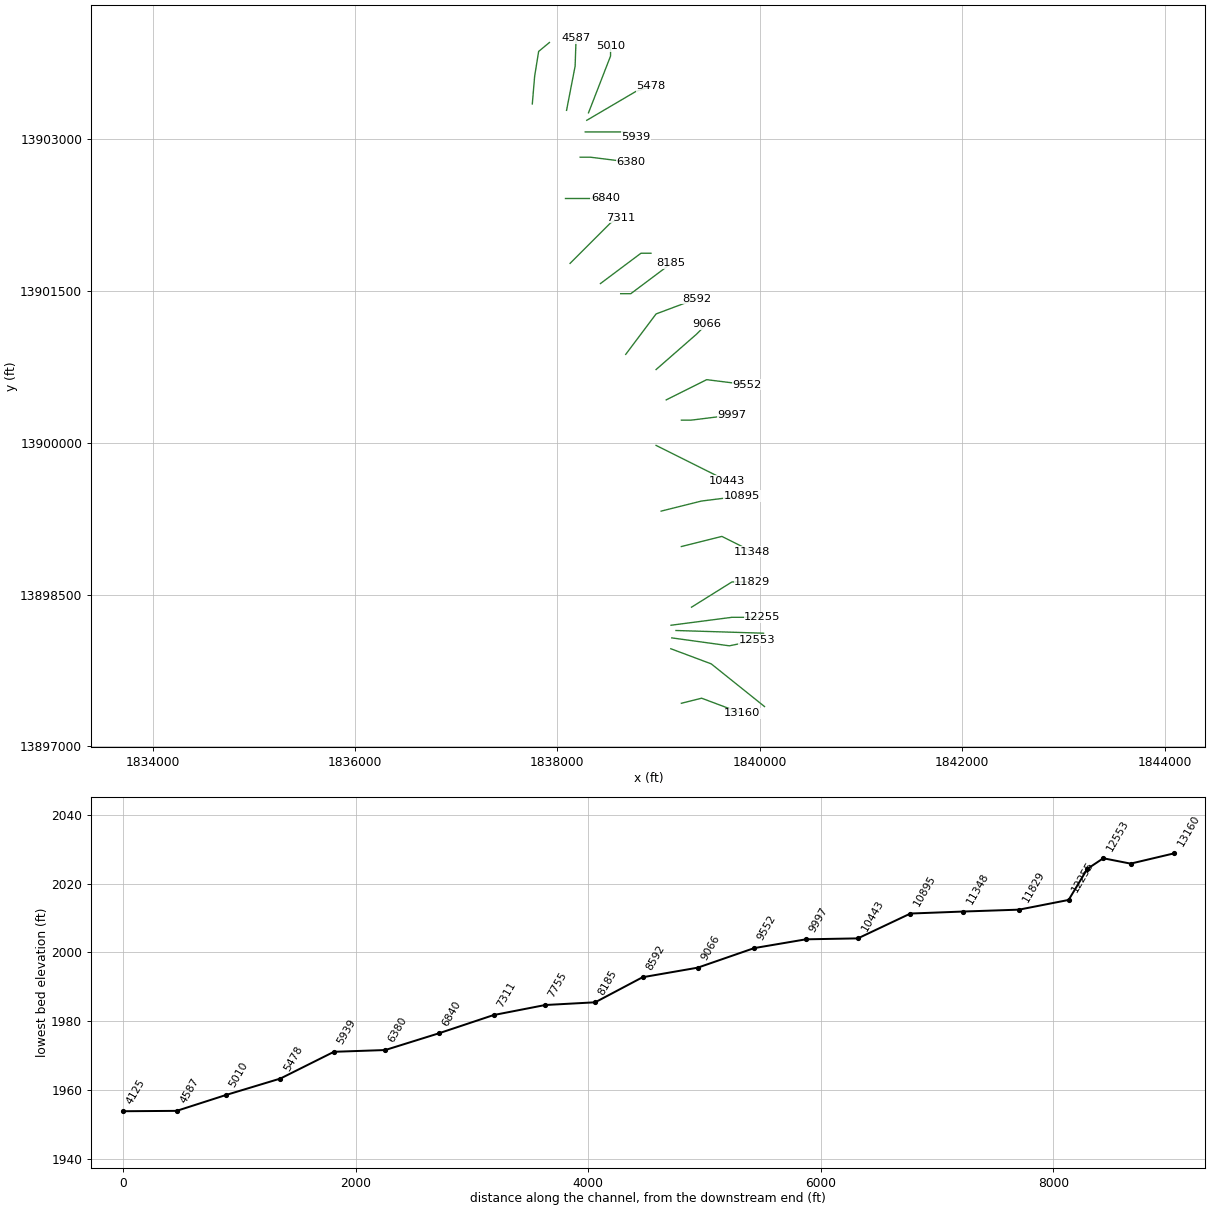
HEC-RAS study Spur Branch.prj: Spur Branch Base Level Engineering

--- Spur Branch.g01 (geometry) --- (continued)

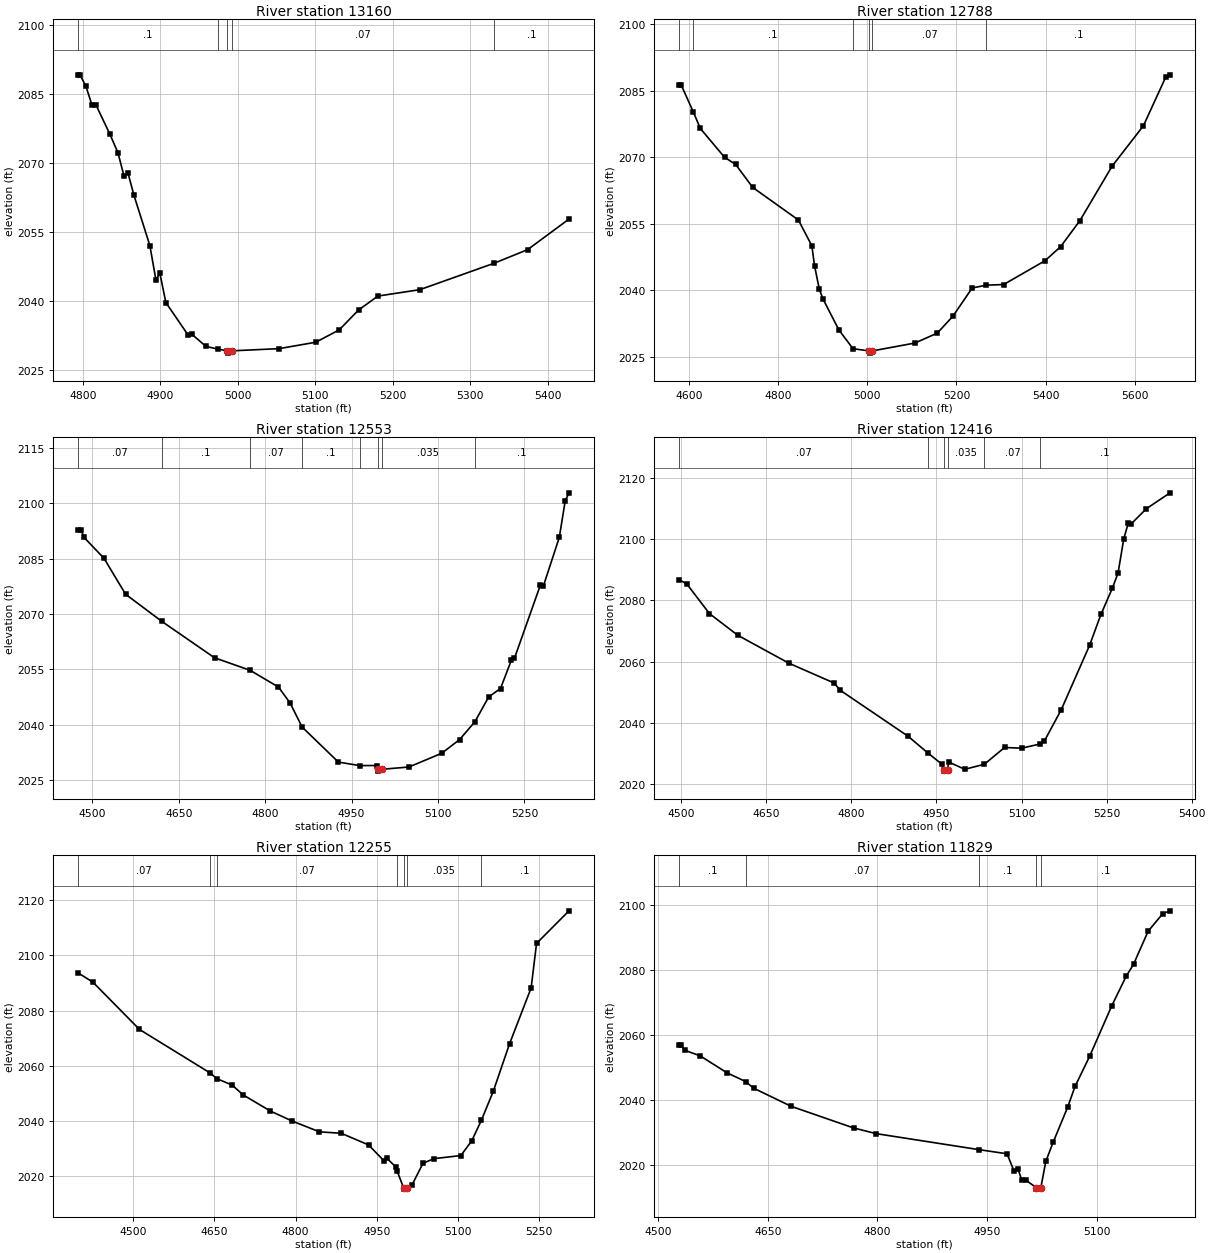
Type RM Length L Ch R = 1,13160,372,372,372
BEGIN DESCRIPTION:
Spur Branch 29.0
END DESCRIPTION:
XS GIS Cut Line= 3
      1839224.97     13897424.99      1839425.00     13897475.00
      1839825.01     13897325.00
#Sta/Elev= 30
  4793.9 2089.23  4796.5 2089.23  4804.2 2086.72  4812.0 2082.65  4817.1 2082.70
  4835.2 2076.29  4845.5 2072.30  4853.2 2067.29  4858.4 2067.92  4866.1 2063.07
  4886.7 2052.11  4894.4 2044.72  4899.6 2046.08  4907.3 2039.75  4935.7 2032.76
  4940.8 2032.87  4958.9 2030.24  4974.3 2029.65  4986.6 2029.27  4987.1 2028.77
  4993.0 2029.27  5053.5 2029.75  5100.7 2031.14  5130.9 2033.82  5155.8 2038.13
  5180.8 2041.17  5235.0 2042.56  5330.6 2048.29  5373.9 2051.25  5427.3 2057.89
#Mann=5,-1,0
  4793.9     0.1       0  4974.3    0.07       0  4986.6    0.05       0
  4993.0    0.07       0  5330.6     0.1       0
Bank Sta=4986.6,4993
Exp/Cntr=0.3,0.1

Type RM Length L Ch R = 1,12788,235,235,235
BEGIN DESCRIPTION:
Spur Branch 28.0
END DESCRIPTION:
XS GIS Cut Line= 3
      1839120.30     13897964.31      1839519.86     13897814.65
      1840046.53     13897392.57
#Sta/Elev= 30
  4577.6 2086.22  4582.8 2086.22  4609.3 2080.28  4625.3 2076.49  4679.7 2069.98
  4704.7 2068.36  4742.8 2063.19  4845.4 2055.83  4875.6 2050.01  4881.6 2045.54
  4892.3 2040.21  4900.6 2038.01  4936.2 2031.04  4968.0 2026.79  5004.8 2026.30
  5005.3 2025.80  5011.3 2026.30  5107.0 2028.08  5156.9 2030.31  5192.1 2034.13
  5235.3 2040.50  5267.3 2041.13  5305.8 2041.27  5398.6 2046.64  5433.8 2049.83
  5477.0 2055.69  5549.0 2067.95  5619.5 2077.10  5669.1 2087.98  5679.2 2088.58
#Mann=6,-1,0
  4577.6    0.07       0  4609.3     0.1       0  4968.0    0.07       0
  5004.8    0.05       0  5011.3    0.07       0  5267.3     0.1       0
Bank Sta=5004.8,5011.3
Exp/Cntr=0.3,0.1

Type RM Length L Ch R = 1,12553,137,137,137
BEGIN DESCRIPTION:
Mapping XS 90660a0a
END DESCRIPTION:
XS GIS Cut Line= 3
      1839130.13     13898071.55      1839699.25     13897992.99
      1839971.42     13898049.58
#Sta/Elev= 30
  4474.9 2092.81  4479.9 2092.81  4485.6 2090.72  4520.2 2085.05  4557.5 2075.34
  4620.1 2068.01  4712.0 2058.10  4773.8 2054.70  4823.0 2050.16  4843.2 2045.83
  4864.1 2039.31  4927.0 2029.81  4964.1 2028.86  4993.9 2028.88  4995.6 2027.86
  4996.1 2027.36  5002.2 2027.86  5049.4 2028.47  5106.4 2032.20  5137.5 2035.92
  5164.0 2040.75  5188.1 2047.50  5208.5 2049.76  5227.5 2057.51  5232.6 2057.92
  5277.6 2077.76  5282.7 2077.45  5310.6 2090.76  5320.8 2100.64  5327.4 2102.83
#Mann=8,-1,0
  4474.9    0.07       0  4620.1     0.1       0  4773.8    0.07       0
  4864.1     0.1       0  4964.1   0.035       0  4995.6   0.035       0
  5002.2   0.035       0  5164.0     0.1       0
Bank Sta=4995.6,5002.2
Exp/Cntr=0.3,0.1

Type RM Length L Ch R = 1,12416,161,161,161
BEGIN DESCRIPTION:
Mapping XS 174cf1fe
END DESCRIPTION:
XS GIS Cut Line= 2
      1839171.42     13898144.58      1840036.70     13898117.83
#Sta/Elev= 30
  4496.2 2086.72  4509.8 2085.36  4549.8 2075.66  4599.8 2068.59  4689.9 2059.48
  4769.9 2052.99  4779.9 2050.71  4900.0 2035.66  4935.8 2030.06  4960.0 2026.50
  4963.2 2024.78  4963.7 2024.28  4969.8 2024.78  4971.5 2027.26  5000.0 2024.88
  5034.5 2026.52  5070.1 2031.99  5100.1 2031.76  5133.2 2033.15  5140.1 2034.02
  5170.1 2044.31  5220.1 2065.35  5240.1 2075.42  5260.1 2083.92  5270.2 2088.87
  5280.2 2099.93  5288.4 2105.34  5293.4 2104.92  5320.2 2109.88  5361.9 2115.05
#Mann=6,-1,0
  4496.2    0.07       0  4935.8   0.035       0  4963.2   0.035       0
  4969.8   0.035       0  5034.5    0.07       0  5133.2     0.1       0
Bank Sta=4963.2,4969.8
Exp/Cntr=0.3,0.1

Type RM Length L Ch R = 1,12255,426,426,426
BEGIN DESCRIPTION:
Spur Branch 27.0
END DESCRIPTION:
XS GIS Cut Line= 3
      1839122.22     13898196.49      1839725.00     13898275.00
      1840025.03     13898275.00
#Sta/Elev= 30
  4397.6 2093.66  4425.2 2090.29  4511.3 2073.14  4641.0 2057.48  4654.3 2055.31
  4682.8 2052.95  4702.9 2049.42  4753.4 2043.55  4793.7 2039.92  4844.1 2036.02
  4884.4 2035.49  4934.9 2031.28  4963.4 2025.51  4968.5 2026.49  4985.3 2023.27
  4987.7 2021.82  4999.6 2015.75  5000.1 2015.25  5006.2 2015.75  5015.5 2016.85
  5035.5 2024.60  5055.5 2026.29  5105.5 2027.42  5125.5 2032.69  5143.5 2040.21
  5165.5 2050.71  5195.5 2067.90  5235.5 2088.20  5245.5 2104.32  5305.5 2116.14
#Mann=7,-1,0
  4397.6    0.07       0  4641.0     0.1       0  4654.3    0.07       0
  4987.7   0.035       0  4999.6   0.035       0  5006.2   0.035       0
  5143.5     0.1       0
Bank Sta=4999.6,5006.2
Exp/Cntr=0.3,0.1

Type RM Length L Ch R = 1,11829,481,481,481
BEGIN DESCRIPTION:
Spur Branch 26.0
END DESCRIPTION:
XS GIS Cut Line= 3
      1839325.02     13898375.01      1839725.00     13898625.00
      1839925.02     13898625.00
#Sta/Elev= 30
  4528.7 2056.83  4531.6 2056.83  4536.3 2055.23  4557.6 2053.50  4594.1 2048.30
  4619.7 2045.59  4630.7 2043.54  4682.0 2037.95  4767.5 2031.28  4798.1 2029.54
  4938.9 2024.60  4977.4 2023.32  4986.8 2018.09  4992.7 2018.48  4997.4 2015.23
  5002.9 2015.23  5017.1 2012.93  5017.6 2012.43  5023.7 2012.93  5030.4 2020.96
  5040.4 2026.82  5060.4 2037.72  5070.4 2044.06  5090.4 2053.36  5120.4 2068.79
  5140.4 2078.03  5150.4 2081.68  5170.4 2091.89  5190.4 2097.31  5200.4 2098.18
#Mann=5,-1,0
  4528.7     0.1       0  4619.7    0.07       0  4938.9     0.1       0
  5017.1    0.05       0  5023.7     0.1       0
Bank Sta=5017.1,5023.7
Exp/Cntr=0.3,0.1

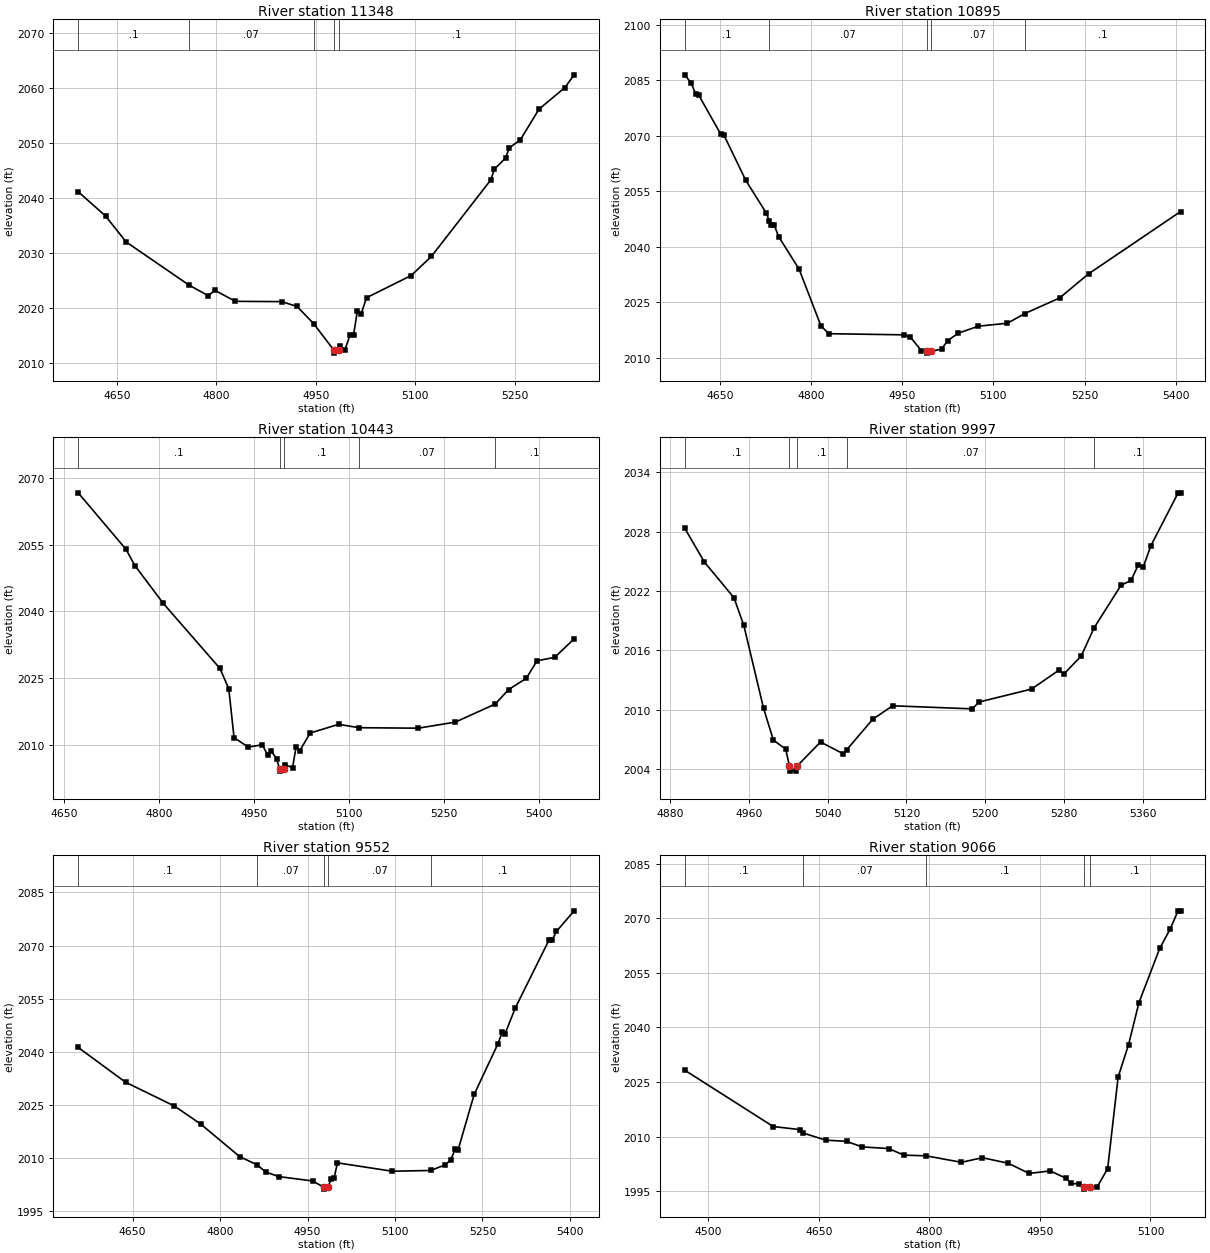
Type RM Length L Ch R = 1,11348,453,453,453
BEGIN DESCRIPTION:
Spur Branch 25.0
END DESCRIPTION:
XS GIS Cut Line= 3
      1839225.00     13898975.00      1839625.00     13899075.00
      1839924.98     13898925.01
#Sta/Elev= 30
  4591.6 2041.15  4632.8 2036.75  4663.8 2032.05  4758.1 2024.26  4787.4 2022.31
  4797.8 2023.25  4828.7 2021.27  4898.3 2021.22  4921.4 2020.35  4946.4 2017.25
  4977.3 2012.38  4977.8 2011.88  4984.1 2012.38  4985.9 2013.15  4993.6 2012.44
  5001.3 2015.12  5006.7 2015.12  5012.3 2019.43  5017.9 2018.93  5026.3 2021.93
  5093.4 2025.94  5124.1 2029.42  5213.5 2043.27  5219.1 2045.25  5235.9 2047.26
  5241.5 2049.10  5258.3 2050.58  5286.2 2056.11  5325.3 2060.04  5339.3 2062.35
#Mann=5,-1,0
  4591.6     0.1       0  4758.1    0.07       0  4946.4     0.1       0
  4977.3    0.05       0  4984.1     0.1       0
Bank Sta=4977.3,4984.1
Exp/Cntr=0.3,0.1

Type RM Length L Ch R = 1,10895,452,452,452
BEGIN DESCRIPTION:
Spur Branch 24.0
END DESCRIPTION:
XS GIS Cut Line= 3
      1839024.95     13899324.99      1839425.00     13899425.00
      1839825.03     13899475.00
#Sta/Elev= 30
  4592.3 2086.49  4602.7 2084.35  4610.4 2081.34  4615.5 2080.98  4651.6 2070.45
  4656.8 2070.22  4692.8 2057.97  4726.3 2049.20  4731.4 2047.08  4734.1 2045.96
  4739.2 2046.01  4747.0 2042.75  4780.5 2033.95  4816.5 2018.62  4829.4 2016.55
  4953.1 2016.24  4963.4 2015.63  4981.5 2011.98  4990.8 2011.80  4991.3 2011.30
  4997.9 2011.80  5014.7 2012.39  5024.8 2014.68  5042.4 2016.70  5075.2 2018.58
  5123.1 2019.38  5151.3 2021.97  5208.7 2026.19  5256.6 2032.74  5407.8 2049.56
#Mann=5,-1,0
  4592.3     0.1       0  4731.4    0.07       0  4990.8    0.05       0
  4997.9    0.07       0  5151.3     0.1       0
Bank Sta=4990.8,4997.9
Exp/Cntr=0.3,0.1

Type RM Length L Ch R = 1,10443,446,446,446
BEGIN DESCRIPTION:
Spur Branch 23.0
END DESCRIPTION:
XS GIS Cut Line= 3
      1838975.02     13899974.99      1839275.00     13899825.00
      1839675.00     13899625.00
#Sta/Elev= 30
  4672.4 2066.63  4747.8 2053.93  4761.8 2050.28  4806.5 2041.81  4896.0 2027.17
  4910.0 2022.60  4918.3 2011.61  4940.7 2009.49  4963.1 2010.00  4971.5 2007.60
  4977.0 2008.60  4985.4 2006.90  4990.2 2004.58  4990.7 2004.08  4997.5 2004.58
  4999.4 2005.44  5010.6 2004.86  5016.2 2009.53  5021.8 2008.62  5038.5 2012.64
  5083.3 2014.60  5115.5 2013.84  5209.0 2013.73  5267.7 2015.11  5330.6 2019.17
  5351.6 2022.42  5379.5 2024.94  5396.3 2028.86  5424.3 2029.66  5455.0 2033.80
#Mann=5,-1,0
  4672.4     0.1       0  4990.2    0.05       0  4997.5     0.1       0
  5115.5    0.07       0  5330.6     0.1       0
Bank Sta=4990.2,4997.5
Exp/Cntr=0.3,0.1

Type RM Length L Ch R = 1,9997,445,445,445
BEGIN DESCRIPTION:
Spur Branch 22.0
END DESCRIPTION:
XS GIS Cut Line= 3
      1839225.00     13900225.00      1839325.00     13900225.00
      1839724.99     13900275.00
#Sta/Elev= 30
  4895.0 2028.35  4915.0 2024.93  4945.0 2021.32  4955.0 2018.53  4975.0 2010.16
  4985.0 2006.94  4997.5 2006.03  5001.3 2004.31  5001.8 2003.81  5008.4 2003.81
  5008.9 2004.31  5032.8 2006.75  5055.5 2005.58  5059.4 2005.97  5085.7 2009.04
  5105.9 2010.41  5186.5 2010.10  5194.0 2010.80  5246.9 2012.10  5274.7 2014.01
  5279.7 2013.62  5297.3 2015.44  5310.2 2018.26  5337.6 2022.58  5347.7 2023.07
  5355.3 2024.66  5360.3 2024.47  5367.9 2026.57  5395.6 2031.92  5398.1 2031.92
#Mann=5,-1,0
  4895.0     0.1       0  5001.3    0.05       0  5008.9     0.1       0
  5059.4    0.07       0  5310.2     0.1       0
Bank Sta=5001.3,5008.9
Exp/Cntr=0.3,0.1

Type RM Length L Ch R = 1,9552,486,486,486
BEGIN DESCRIPTION:
Spur Branch 21.0
END DESCRIPTION:
XS GIS Cut Line= 3
      1839074.96     13900424.98      1839475.00     13900625.00
      1839875.03     13900575.00
#Sta/Elev= 30
  4556.8 2041.25  4637.9 2031.44  4721.8 2024.71  4766.5 2019.67  4833.6 2010.45
  4863.9 2008.08  4878.3 2006.10  4900.6 2004.80  4959.3 2003.55  4977.9 2001.76
  4978.4 2001.26  4985.5 2001.76  4990.1 2004.19  4995.7 2004.50  5001.3 2008.68
  5094.8 2006.32  5161.1 2006.52  5185.5 2008.07  5195.5 2009.46  5203.1 2012.51
  5208.1 2012.28  5235.8 2028.01  5276.2 2042.17  5283.7 2045.48  5288.8 2045.15
  5306.4 2052.43  5364.3 2071.64  5369.4 2071.57  5376.9 2074.02  5407.2 2079.81
#Mann=5,-1,0
  4556.8     0.1       0  4863.9    0.07       0  4977.9    0.05       0
  4985.5    0.07       0  5161.1     0.1       0
Bank Sta=4977.9,4985.5
Exp/Cntr=0.3,0.1

Type RM Length L Ch R = 1,9066,474,474,474
BEGIN DESCRIPTION:
Spur Branch 20.0
END DESCRIPTION:
XS GIS Cut Line= 3
      1838975.00     13900725.00      1839375.00     13901075.00
      1839474.98     13901174.98
#Sta/Elev= 30
  4468.0 2028.26  4588.1 2012.77  4624.1 2011.93  4629.0 2010.98  4659.3 2009.03
  4687.7 2008.69  4708.6 2007.18  4744.7 2006.71  4765.6 2004.91  4795.5 2004.72
  4843.4 2002.94  4871.9 2004.20  4907.0 2002.68  4935.4 1999.88  4963.9 2000.58
  4985.8 1998.52  4992.4 1997.13  5003.0 1997.00  5009.8 1996.07  5010.3 1995.57
  5017.5 1996.07  5027.8 1996.22  5041.9 2001.20  5056.1 2026.36  5070.2 2035.23
  5084.4 2046.84  5112.6 2061.74  5126.8 2067.06  5137.4 2072.04  5140.9 2072.04
#Mann=5,-1,0
  4468.0     0.1       0  4629.0    0.07       0  4795.5     0.1       0
  5009.8    0.05       0  5017.5     0.1       0
Bank Sta=5009.8,5017.5
Exp/Cntr=0.3,0.1

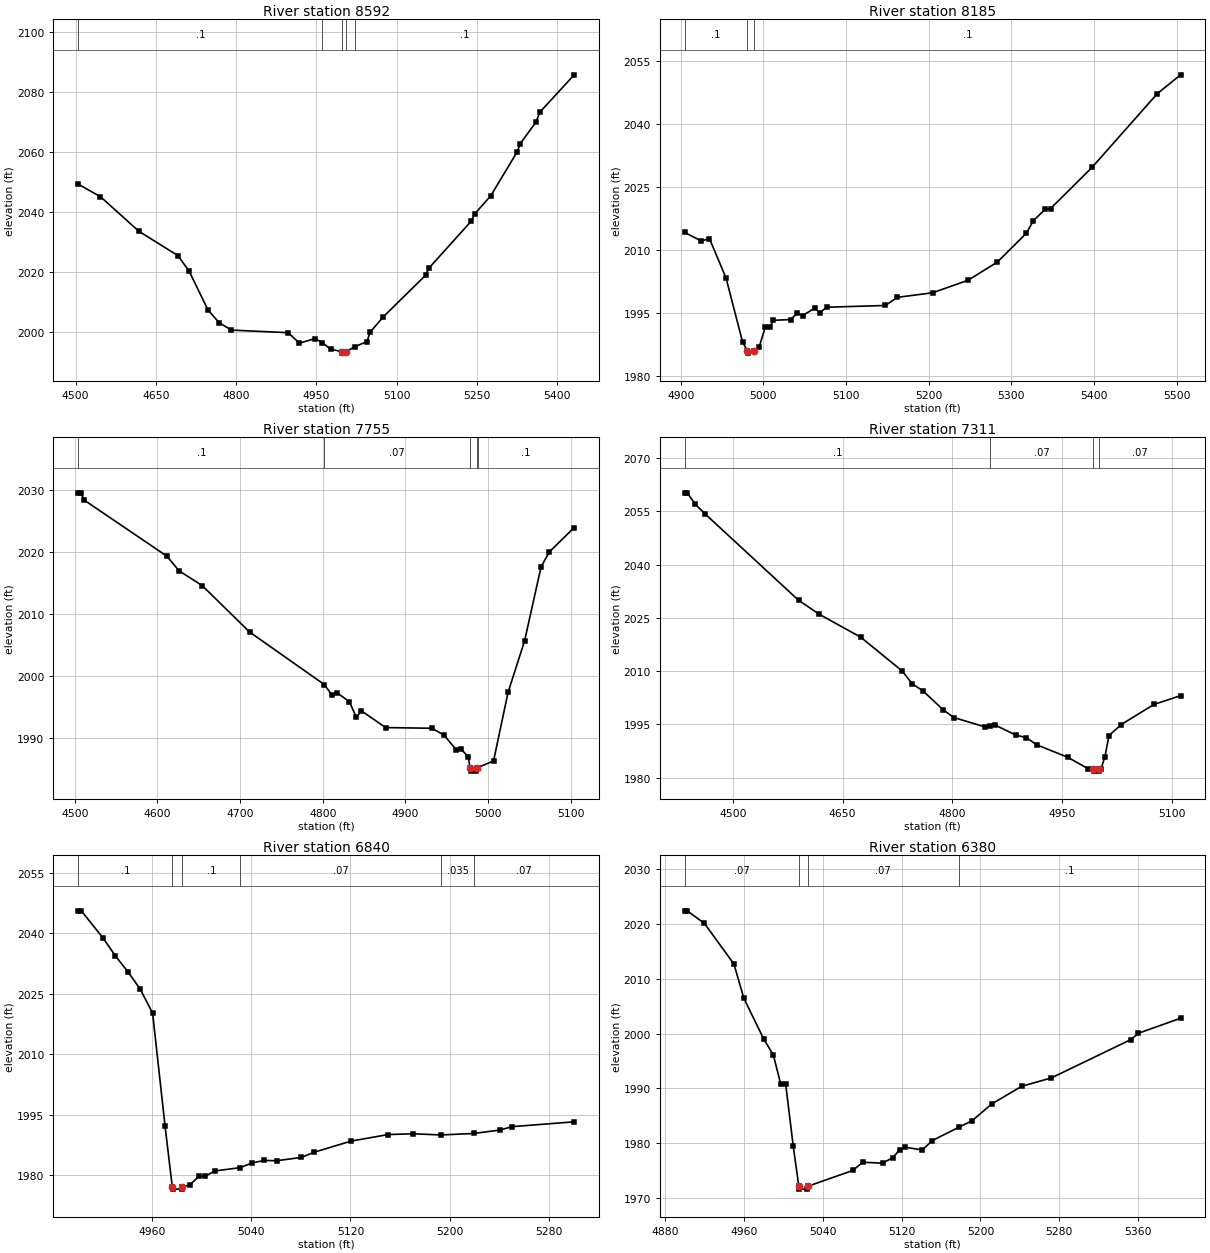
Type RM Length L Ch R = 1,8592,407,407,407
BEGIN DESCRIPTION:
Spur Branch 19.0
END DESCRIPTION:
XS GIS Cut Line= 3
      1838675.02     13900875.03      1838975.00     13901275.00
      1839375.04     13901425.01
#Sta/Elev= 30
  4504.8 2049.19  4546.4 2045.00  4618.3 2033.44  4691.2 2025.34  4712.1 2020.16
  4747.5 2007.17  4768.3 2002.95  4791.2 2000.48  4897.5 1999.61  4918.3 1996.11
  4947.5 1997.64  4961.4 1996.30  4976.6 1994.10  4997.7 1993.29  4998.2 1992.79
  5005.5 1993.29  5021.9 1994.91  5044.8 1996.66  5050.2 1999.70  5075.1 2004.90
  5154.3 2018.77  5160.5 2021.17  5239.7 2036.85  5246.0 2039.24  5276.2 2045.33
  5325.2 2059.89  5331.4 2062.75  5360.8 2069.93  5367.9 2073.20  5432.0 2085.67
#Mann=5,-1,0
  4504.8     0.1       0  4961.4    0.07       0  4997.7    0.05       0
  5005.5    0.07       0  5021.9     0.1       0
Bank Sta=4997.7,5005.5
Exp/Cntr=0.3,0.1

Type RM Length L Ch R = 1,8185,430,430,430
BEGIN DESCRIPTION:
Spur Branch 18.0
END DESCRIPTION:
XS GIS Cut Line= 3
      1838625.04     13901475.00      1838725.00     13901475.00
      1839125.03     13901775.02
#Sta/Elev= 30
  4904.9 2014.24  4924.9 2012.22  4934.9 2012.76  4954.9 2003.42  4974.9 1988.20
  4980.9 1986.01  4981.4 1985.51  4988.9 1986.01  4994.9 1986.88  5002.4 1991.70
  5008.0 1991.70  5012.2 1993.32  5033.0 1993.50  5041.3 1995.01  5047.6 1994.45
  5062.2 1996.21  5068.4 1995.14  5076.7 1996.44  5147.6 1996.85  5162.2 1998.79
  5204.9 1999.88  5247.6 2002.85  5283.0 2007.16  5318.4 2014.07  5326.7 2017.03
  5341.3 2019.80  5347.6 2019.93  5397.6 2029.70  5476.7 2047.28  5504.9 2051.76
#Mann=3,-1,0
  4904.9     0.1       0  4980.9    0.05       0  4988.9     0.1       0
Bank Sta=4980.9,4988.9
Exp/Cntr=0.3,0.1

Type RM Length L Ch R = 1,7755,444,444,444
BEGIN DESCRIPTION:
Spur Branch 17.0
END DESCRIPTION:
XS GIS Cut Line= 3
      1838425.01     13901575.01      1838825.00     13901875.00
      1838925.01     13901875.00
#Sta/Elev= 30
  4504.2 2029.52  4507.3 2029.52  4511.5 2028.34  4611.5 2019.32  4626.1 2016.98
  4654.2 2014.59  4711.5 2007.12  4802.1 1998.64  4811.5 1996.90  4817.7 1997.30
  4832.3 1995.89  4840.6 1993.40  4846.9 1994.42  4876.1 1991.73  4932.3 1991.62
  4946.9 1990.49  4961.5 1988.17  4967.7 1988.24  4976.1 1986.99  4978.3 1985.22
  4978.8 1984.72  4985.8 1984.72  4986.3 1985.22  4987.6 1985.30  5006.7 1986.36
  5024.2 1997.38  5044.2 2005.68  5064.2 2017.61  5074.2 2020.01  5104.2 2023.92
#Mann=5,-1,0
  4504.2     0.1       0  4802.1    0.07       0  4978.3    0.05       0
  4986.3    0.07       0  4987.6     0.1       0
Bank Sta=4978.3,4986.3
Exp/Cntr=0.3,0.1

Type RM Length L Ch R = 1,7311,471,471,471
BEGIN DESCRIPTION:
Spur Branch 16.0
END DESCRIPTION:
XS GIS Cut Line= 3
      1838125.01     13901775.01      1838525.00     13902175.00
      1838625.02     13902225.01
#Sta/Elev= 30
  4434.3 2060.23  4437.8 2060.23  4448.4 2057.09  4462.6 2054.21  4589.9 2029.95
  4618.1 2026.00  4674.7 2019.56  4731.3 2010.04  4745.4 2006.36  4759.6 2004.45
  4787.8 1999.03  4802.0 1996.90  4844.4 1994.27  4851.8 1994.53  4858.6 1994.77
  4886.8 1991.94  4901.0 1991.26  4915.1 1989.23  4957.5 1985.71  4985.8 1982.45
  4992.4 1982.30  4992.9 1981.80  5000.0 1981.80  5000.5 1982.30  5002.8 1982.30
  5008.4 1985.84  5013.9 1991.82  5030.7 1994.94  5075.4 2000.59  5111.8 2003.08
#Mann=4,-1,0
  4434.3     0.1       0  4851.8    0.07       0  4992.4    0.05       0
  5000.5    0.07       0
Bank Sta=4992.4,5000.5
Exp/Cntr=0.3,0.1

Type RM Length L Ch R = 1,6840,460,460,460
BEGIN DESCRIPTION:
Spur Branch 15.0
END DESCRIPTION:
XS GIS Cut Line= 3
      1838074.98     13902425.00      1838175.00     13902425.00
      1838474.98     13902425.00
#Sta/Elev= 30
  4900.4 2045.58  4902.9 2045.58  4920.4 2038.84  4930.4 2034.39  4940.4 2030.49
  4950.4 2026.14  4960.4 2020.18  4970.4 1992.26  4976.3 1976.99  4976.8 1976.49
  4984.0 1976.49  4984.5 1976.99  4990.4 1977.55  4997.9 1979.68  5002.9 1979.68
  5010.4 1980.99  5031.1 1981.83  5040.4 1982.97  5050.4 1983.62  5060.4 1983.54
  5080.4 1984.36  5090.4 1985.62  5120.4 1988.41  5150.4 1990.04  5170.4 1990.23
  5193.1 1989.94  5219.6 1990.31  5240.4 1991.15  5250.4 1992.00  5300.4 1993.20
#Mann=6,-1,0
  4900.4     0.1       0  4976.3    0.05       0  4984.5     0.1       0
  5031.1    0.07       0  5193.1   0.035       0  5219.6    0.07       0
Bank Sta=4976.3,4984.5
Exp/Cntr=0.3,0.1

Type RM Length L Ch R = 1,6380,441,441,441
BEGIN DESCRIPTION:
Spur Branch 14.0
END DESCRIPTION:
XS GIS Cut Line= 3
      1838225.00     13902825.00      1838325.00     13902825.00
      1838724.99     13902775.00
#Sta/Elev= 30
  4900.0 2022.41  4902.5 2022.41  4920.0 2020.13  4950.0 2012.69  4960.0 2006.47
  4980.0 1999.09  4990.0 1996.08  4997.5 1990.75  5002.5 1990.75  5010.1 1979.52
  5015.8 1972.14  5016.3 1971.64  5024.1 1971.64  5024.6 1972.14  5070.5 1975.04
  5080.6 1976.54  5100.8 1976.38  5110.9 1977.36  5118.4 1978.84  5123.5 1979.28
  5141.1 1978.79  5151.2 1980.50  5177.9 1982.91  5191.5 1984.11  5211.6 1987.19
  5241.9 1990.40  5272.1 1991.94  5352.7 1998.93  5360.3 2000.08  5403.1 2002.82
#Mann=4,-1,0
  4900.0    0.07       0  5015.8    0.05       0  5024.6    0.07       0
  5177.9     0.1       0
Bank Sta=5015.8,5024.6
Exp/Cntr=0.3,0.1

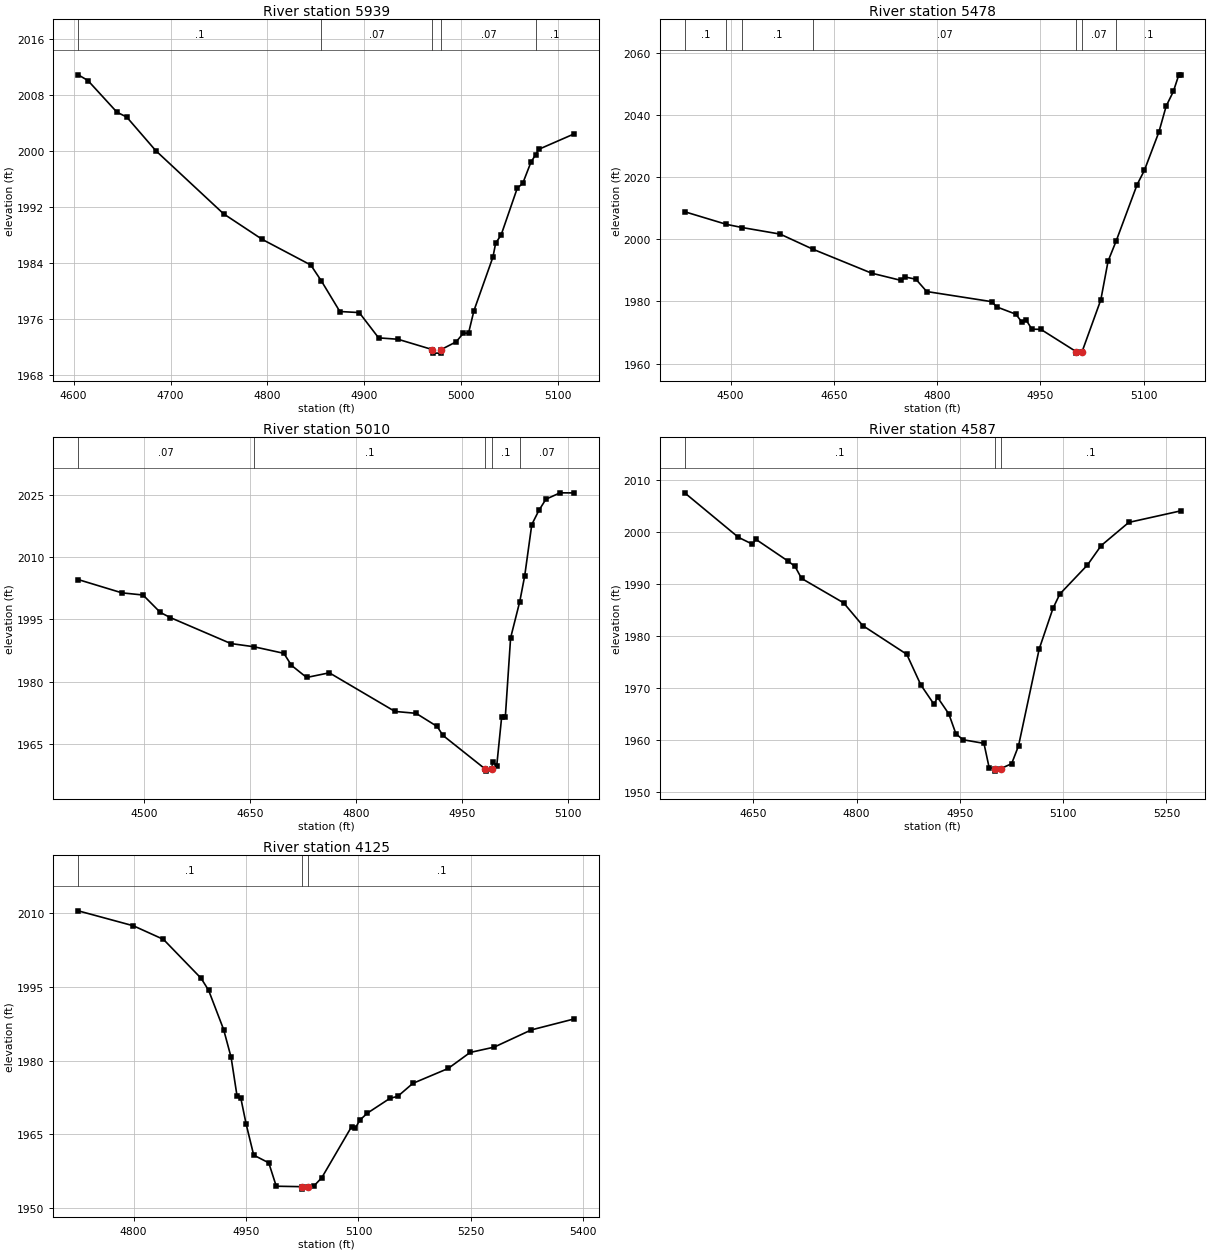
Type RM Length L Ch R = 1,5939,461,461,461
BEGIN DESCRIPTION:
Spur Branch 13.0
END DESCRIPTION:
XS GIS Cut Line= 3
      1838274.97     13903075.00      1838675.00     13903075.00
      1838774.97     13903025.02
#Sta/Elev= 30
  4604.7 2010.86  4614.7 2010.05  4644.7 2005.52  4654.7 2004.84  4684.7 2000.04
  4754.7 1991.02  4794.7 1987.36  4844.7 1983.71  4855.7 1981.42  4874.7 1977.07
  4894.7 1976.92  4914.7 1973.31  4934.7 1973.11  4970.3 1971.63  4970.8 1971.13
  4978.6 1971.13  4979.1 1971.63  4994.7 1972.74  5002.2 1973.98  5007.5 1973.98
  5013.1 1977.20  5032.7 1984.85  5035.5 1986.84  5041.1 1987.98  5057.8 1994.68
  5063.4 1995.35  5071.8 1998.35  5076.8 1999.48  5080.2 2000.24  5116.5 2002.43
#Mann=5,-1,0
  4604.7     0.1       0  4855.7    0.07       0  4970.3    0.05       0
  4979.1    0.07       0  5076.8     0.1       0
Bank Sta=4970.3,4979.1
Exp/Cntr=0.3,0.1

Type RM Length L Ch R = 1,5478,468,468,468
BEGIN DESCRIPTION:
Spur Branch 12.0
END DESCRIPTION:
XS GIS Cut Line= 3
      1838290.27     13903189.77      1838775.00     13903475.00
      1838924.96     13903524.99
#Sta/Elev= 30
  4433.2 2008.82  4493.7 2004.77  4516.4 2003.75  4571.9 2001.63  4619.4 1996.78
  4704.7 1989.07  4747.7 1986.73  4753.5 1987.83  4769.1 1987.12  4784.8 1983.16
  4879.6 1979.89  4886.3 1978.23  4914.4 1975.87  4923.4 1973.21  4929.2 1974.02
  4937.6 1971.06  4950.7 1970.99  5001.8 1963.85  5002.3 1963.35  5010.6 1963.85
  5037.8 1980.52  5048.3 1992.92  5060.2 1999.49  5090.5 2017.54  5101.0 2022.10
  5122.1 2034.42  5132.7 2042.78  5143.2 2047.53  5151.1 2052.85  5153.7 2052.85
#Mann=7,-1,0
  4433.2     0.1       0  4493.7    0.07       0  4516.4     0.1       0
  4619.4    0.07       0  5001.8    0.05       0  5010.6    0.07       0
  5060.2     0.1       0
Bank Sta=5001.8,5010.6
Exp/Cntr=0.3,0.1

Type RM Length L Ch R = 1,5010,423,423,423
BEGIN DESCRIPTION:
Spur Branch 11.0
END DESCRIPTION:
XS GIS Cut Line= 3
      1838307.18     13903263.49      1838525.00     13903825.00
      1838525.00     13903925.02
#Sta/Elev= 30
  4406.6 2004.59  4468.5 2001.40  4498.4 2000.88  4522.9 1996.69  4536.9 1995.47
  4622.7 1989.22  4655.5 1988.45  4697.8 1986.87  4708.6 1983.98  4730.0 1981.07
  4762.2 1982.19  4855.1 1972.91  4885.0 1972.46  4914.9 1969.30  4923.1 1967.15
  4983.0 1959.07  4983.5 1958.57  4991.9 1959.07  4993.9 1960.71  4999.3 1959.91
  5006.2 1971.51  5011.4 1971.51  5018.9 1990.57  5031.9 1999.32  5038.9 2005.51
  5048.9 2017.80  5058.9 2021.19  5068.9 2023.89  5088.9 2025.43  5108.9 2025.41
#Mann=5,-1,0
  4406.6    0.07       0  4655.5     0.1       0  4983.0    0.05       0
  4991.9     0.1       0  5031.9    0.07       0
Bank Sta=4983,4991.9
Exp/Cntr=0.3,0.1

Type RM Length L Ch R = 1,4587,462,462,462
BEGIN DESCRIPTION:
Spur Branch 10.0
END DESCRIPTION:
XS GIS Cut Line= 3
      1838090.34     13903288.38      1838175.00     13903725.00
      1838184.39     13904000.29
#Sta/Elev= 30
  4550.4 2007.59  4628.4 1999.02  4648.7 1997.70  4653.8 1998.63  4699.8 1994.50
  4710.6 1993.42  4720.1 1991.10  4781.2 1986.39  4809.0 1982.01  4872.9 1976.48
  4893.3 1970.59  4912.5 1966.84  4917.6 1968.19  4934.0 1964.99  4944.2 1961.19
  4954.4 1960.02  4985.0 1959.32  4992.6 1954.61  5000.7 1954.47  5001.2 1953.97
  5009.6 1954.47  5025.2 1955.40  5035.2 1958.84  5065.2 1977.49  5085.2 1985.32
  5095.2 1988.09  5135.2 1993.67  5155.2 1997.42  5195.3 2001.89  5270.6 2004.11
#Mann=3,-1,0
  4550.4     0.1       0  5000.7    0.05       0  5009.6     0.1       0
Bank Sta=5000.7,5009.6
Exp/Cntr=0.3,0.1

Type RM Length L Ch R = 1,4125,457,457,457
BEGIN DESCRIPTION:
Spur Branch 9.0
END DESCRIPTION:
XS GIS Cut Line= 4
      1837751.93     13903351.72      1837775.00     13903625.00
      1837814.47     13903870.75      1837921.08     13903959.09
#Sta/Elev= 30
  4726.1 2010.49  4799.6 2007.45  4839.8 2004.68  4890.0 1996.77  4900.0 1994.34
  4920.1 1986.33  4930.1 1980.65  4938.0 1972.78  4943.0 1972.40  4950.2 1967.04
  4960.2 1960.78  4980.3 1959.21  4990.3 1954.45  5024.3 1954.36  5024.8 1953.86
  5033.2 1954.36  5040.9 1954.56  5051.0 1956.18  5090.7 1966.55  5095.7 1966.24
  5101.6 1967.87  5111.8 1969.32  5142.1 1972.35  5152.3 1972.73  5172.5 1975.38
  5219.6 1978.41  5248.9 1981.67  5280.9 1982.75  5330.4 1986.25  5387.7 1988.49
#Mann=3,-1,0
  4726.1     0.1       0  5024.3    0.05       0  5033.2     0.1       0
Bank Sta=5024.3,5033.2
Exp/Cntr=0.3,0.1