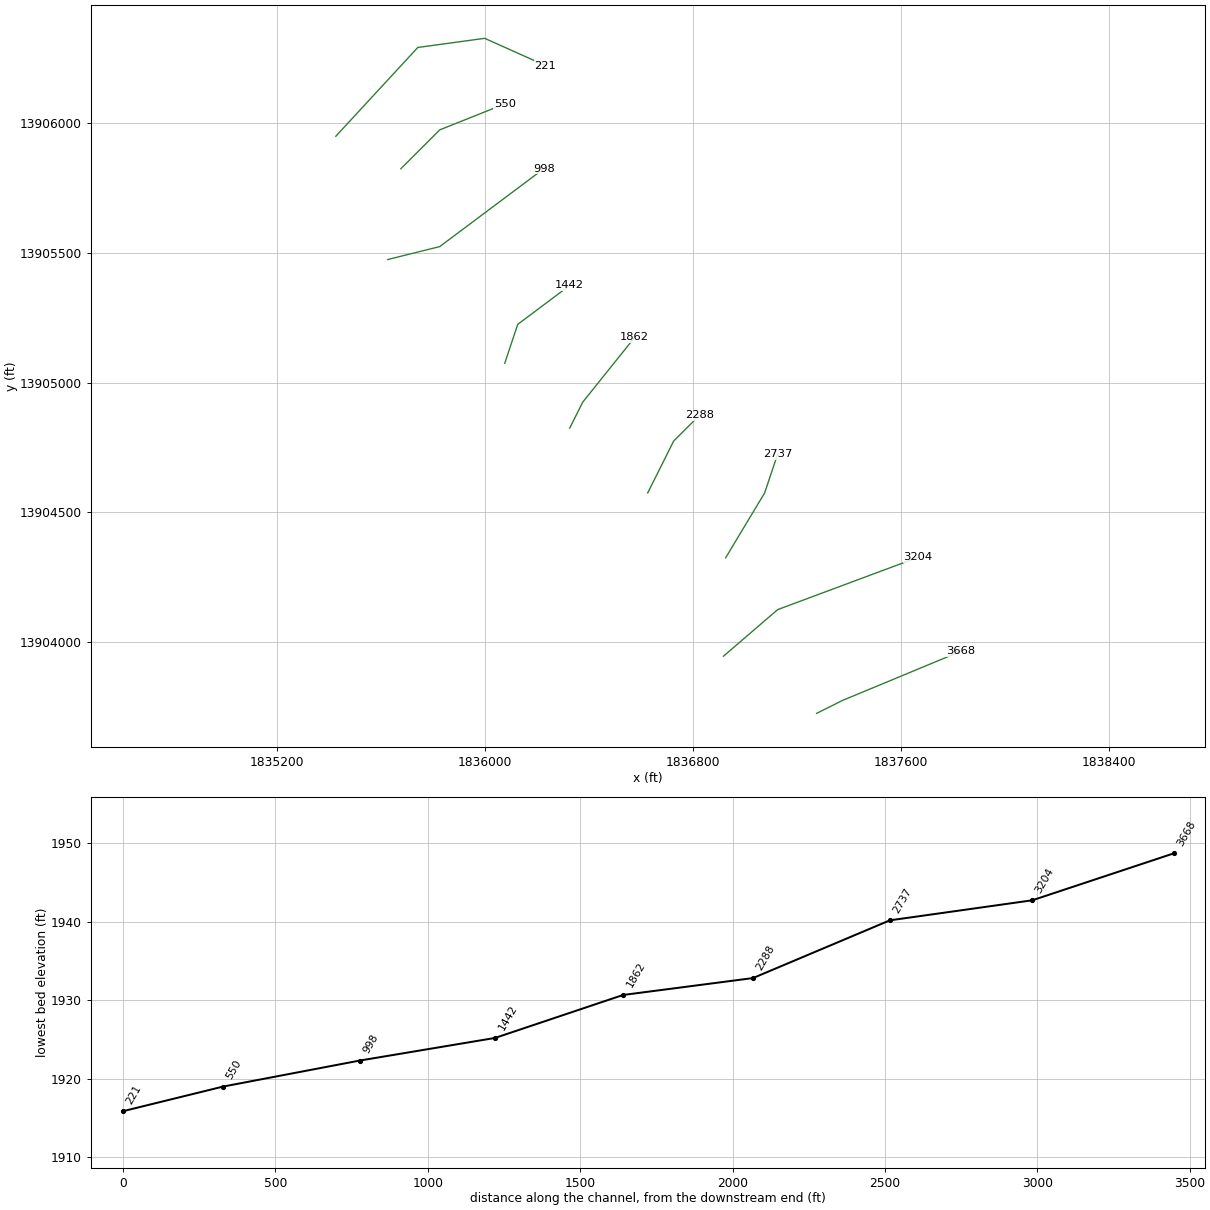
HEC-RAS study Spur Branch.prj: Spur Branch Base Level Engineering

--- Spur Branch.g01 (geometry) --- (continued)

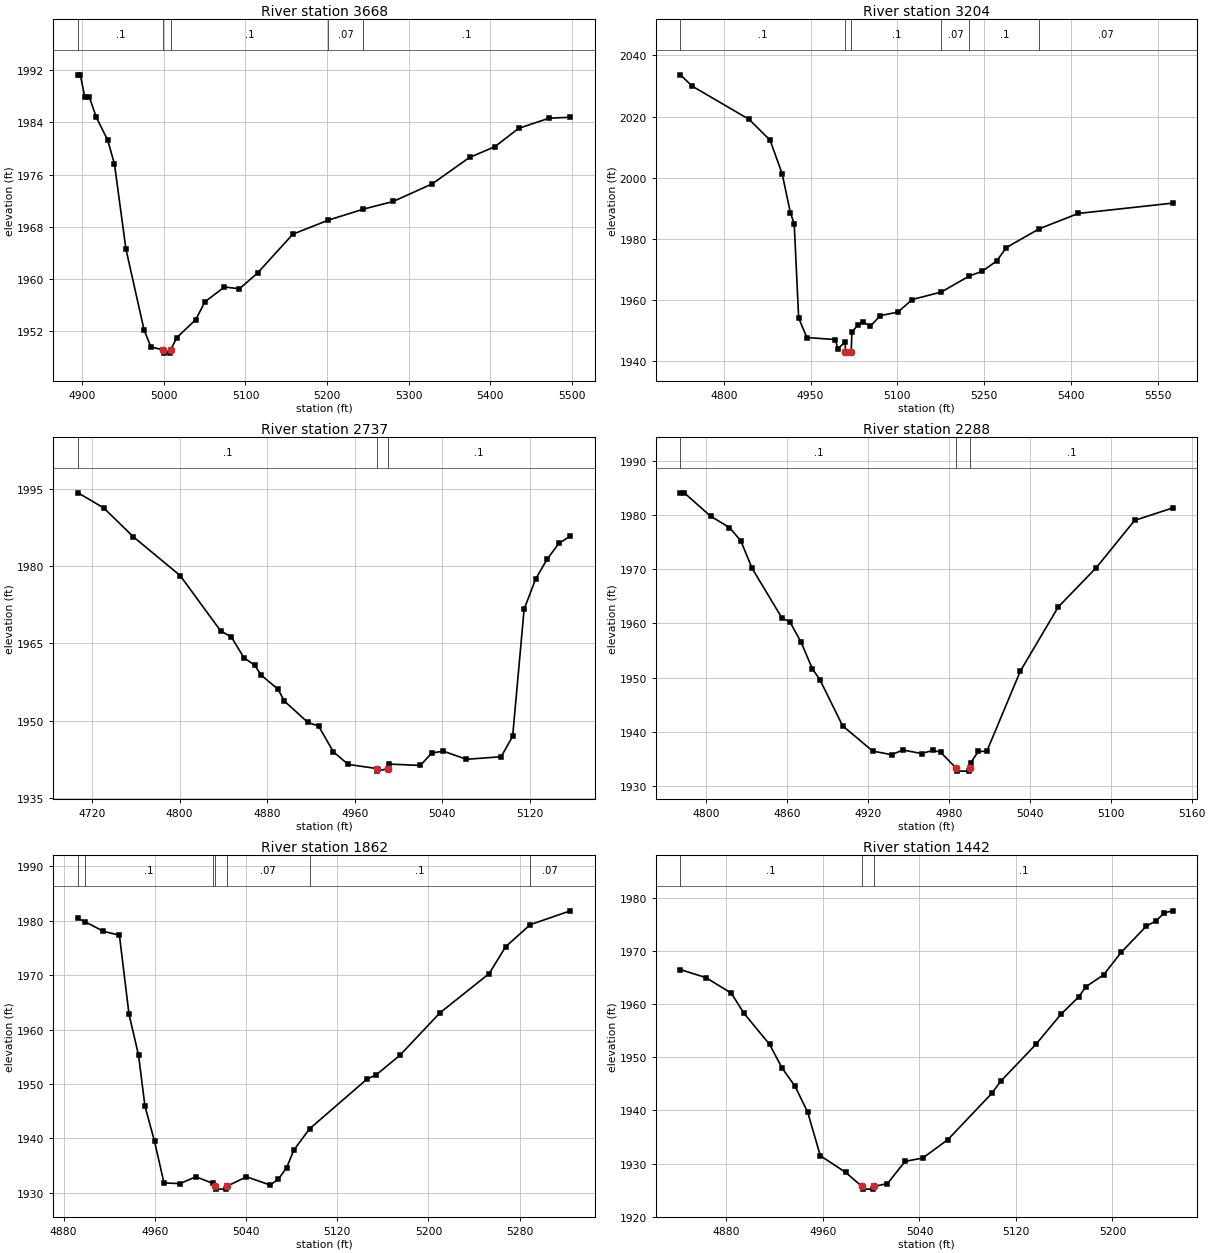
Type RM Length L Ch R = 1,3668,464,464,464
BEGIN DESCRIPTION:
Spur Branch 8.0
END DESCRIPTION:
XS GIS Cut Line= 3
      1837275.01     13903725.00      1837375.00     13903775.00
      1837829.14     13903964.01
#Sta/Elev= 30
  4894.7 1991.29  4897.5 1991.29  4903.1 1987.82  4908.7 1987.82  4917.1 1984.80
  4931.0 1981.31  4939.4 1977.62  4953.4 1964.64  4975.7 1952.23  4984.1 1949.62
  4999.2 1949.18  4999.7 1948.68  5007.8 1948.68  5008.3 1949.18  5015.7 1951.05
  5039.0 1953.80  5050.4 1956.55  5074.2 1958.80  5092.7 1958.54  5114.8 1960.94
  5158.1 1966.89  5201.4 1969.03  5244.7 1970.73  5281.2 1971.90  5328.9 1974.59
  5374.8 1978.64  5405.9 1980.29  5435.1 1983.10  5472.3 1984.65  5498.4 1984.79
#Mann=5,-1,0
  4894.7     0.1       0  4999.2    0.05       0  5008.3     0.1       0
  5201.4    0.07       0  5244.7     0.1       0
Bank Sta=4999.2,5008.3
Exp/Cntr=0.3,0.1

Type RM Length L Ch R = 1,3204,467,467,467
BEGIN DESCRIPTION:
Spur Branch 7.0
END DESCRIPTION:
XS GIS Cut Line= 3
      1836916.63     13903945.50      1837125.00     13904125.00
      1837664.58     13904326.49
#Sta/Elev= 30
  4725.1 2033.68  4745.0 2030.02  4843.8 2019.11  4880.0 2012.31  4900.8 2001.38
  4915.1 1988.60  4921.7 1984.99  4929.4 1954.18  4943.6 1947.81  4993.0 1947.14
  4996.8 1944.16  5009.9 1946.30  5010.3 1943.21  5010.8 1942.71  5020.2 1943.21
  5021.5 1949.66  5032.1 1951.92  5040.2 1952.89  5053.5 1951.54  5070.5 1954.96
  5100.9 1956.13  5125.8 1960.23  5176.1 1962.69  5224.5 1967.94  5247.0 1969.49
  5272.0 1972.88  5288.3 1977.21  5345.7 1983.39  5412.9 1988.37  5576.1 1991.74
#Mann=6,-1,0
  4725.1     0.1       0  5010.3    0.05       0  5020.2     0.1       0
  5176.1    0.07       0  5224.5     0.1       0  5345.7    0.07       0
Bank Sta=5010.3,5020.2
Exp/Cntr=0.3,0.1

Type RM Length L Ch R = 1,2737,449,449,449
BEGIN DESCRIPTION:
Spur Branch 6.0
END DESCRIPTION:
XS GIS Cut Line= 3
      1836924.98     13904324.96      1837075.00     13904575.00
      1837125.00     13904725.00
#Sta/Elev= 30
  4707.2 1994.31  4730.6 1991.38  4757.8 1985.74  4800.5 1978.21  4837.5 1967.44
  4847.2 1966.28  4858.8 1962.20  4868.6 1960.78  4874.4 1958.86  4889.9 1956.09
  4895.8 1953.76  4917.2 1949.63  4926.9 1948.95  4940.5 1943.89  4954.1 1941.46
  4980.2 1940.66  4980.7 1940.16  4990.2 1940.66  4991.0 1941.53  5019.9 1941.27
  5030.4 1943.70  5041.0 1944.04  5062.0 1942.46  5093.7 1942.96  5104.2 1946.92
  5114.7 1971.67  5125.3 1977.58  5135.8 1981.42  5146.4 1984.46  5156.9 1985.90
#Mann=3,-1,0
  4707.2     0.1       0  4980.2    0.05       0  4990.2     0.1       0
Bank Sta=4980.2,4990.2
Exp/Cntr=0.3,0.1

Type RM Length L Ch R = 1,2288,426,426,426
BEGIN DESCRIPTION:
Spur Branch 5.0
END DESCRIPTION:
XS GIS Cut Line= 3
      1836625.02     13904575.03      1836725.00     13904775.00
      1836825.01     13904875.01
#Sta/Elev= 30
  4781.0 1984.05  4783.8 1984.05  4803.3 1979.75  4817.3 1977.66  4825.7 1975.23
  4834.1 1970.15  4856.4 1960.93  4862.0 1960.33  4870.4 1956.57  4878.8 1951.63
  4884.4 1949.63  4901.2 1941.16  4923.5 1936.50  4937.5 1935.84  4945.9 1936.69
  4959.8 1936.05  4968.2 1936.63  4973.8 1936.30  4985.6 1933.31  4986.1 1932.81
  4995.1 1932.81  4995.6 1933.31  4996.2 1934.34  5001.8 1936.45  5008.1 1936.45
  5032.9 1951.19  5061.1 1963.04  5089.4 1970.30  5117.7 1978.97  5146.0 1981.27
#Mann=3,-1,0
  4781.0     0.1       0  4985.6    0.05       0  4995.6     0.1       0
Bank Sta=4985.6,4995.6
Exp/Cntr=0.3,0.1

Type RM Length L Ch R = 1,1862,420,420,420
BEGIN DESCRIPTION:
Spur Branch 4.0
END DESCRIPTION:
XS GIS Cut Line= 3
      1836325.01     13904825.02      1836375.00     13904925.00
      1836574.98     13905174.97
#Sta/Elev= 30
  4892.6 1980.46  4898.7 1979.83  4914.9 1978.06  4928.9 1977.35  4937.3 1962.85
  4945.7 1955.27  4951.3 1945.93  4959.7 1939.46  4968.0 1931.80  4982.0 1931.67
  4996.0 1932.93  5011.1 1931.70  5013.0 1931.16  5013.5 1930.66  5022.5 1930.66
  5023.0 1931.16  5040.4 1932.93  5061.2 1931.41  5068.4 1932.50  5075.6 1934.60
  5082.0 1937.87  5095.8 1941.76  5146.1 1950.89  5154.1 1951.66  5174.9 1955.25
  5210.1 1963.07  5253.3 1970.29  5267.7 1975.22  5289.3 1979.28  5324.5 1981.83
#Mann=7,-1,0
  4892.6    0.07       0  4898.7     0.1       0  5011.1    0.07       0
  5013.0    0.05       0  5023.0    0.07       0  5095.8     0.1       0
  5289.3    0.07       0
Bank Sta=5013,5023
Exp/Cntr=0.3,0.1

Type RM Length L Ch R = 1,1442,444,444,444
BEGIN DESCRIPTION:
Spur Branch 3.0
END DESCRIPTION:
XS GIS Cut Line= 3
      1836075.00     13905075.01      1836125.00     13905225.00
      1836325.00     13905375.00
#Sta/Elev= 30
  4841.9 1966.53  4863.0 1965.02  4884.0 1962.10  4894.6 1958.28  4915.7 1952.47
  4926.2 1947.97  4936.8 1944.58  4947.3 1939.71  4957.8 1931.49  4978.9 1928.33
  4992.3 1925.69  4992.8 1925.19  5001.9 1925.19  5002.4 1925.69  5013.5 1926.24
  5028.1 1930.42  5042.7 1931.04  5063.5 1934.50  5100.0 1943.23  5107.3 1945.49
  5136.5 1952.44  5157.3 1958.13  5171.9 1961.36  5178.1 1963.33  5192.7 1965.55
  5207.3 1969.80  5228.1 1974.72  5236.5 1975.76  5242.7 1977.20  5250.0 1977.60
#Mann=3,-1,0
  4841.9     0.1       0  4992.3    0.05       0  5002.4     0.1       0
Bank Sta=4992.3,5002.4
Exp/Cntr=0.3,0.1

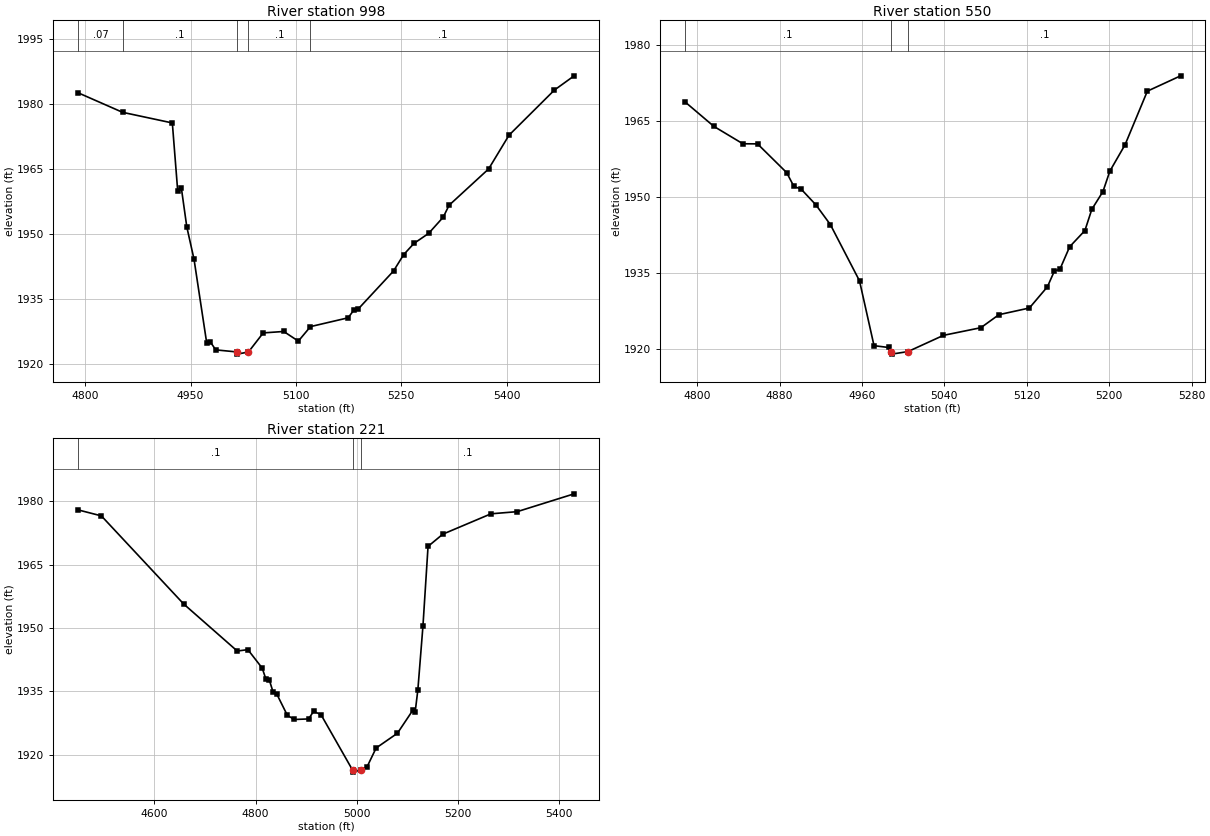
Type RM Length L Ch R = 1,998,448,448,448
BEGIN DESCRIPTION:
Spur Branch 2.0
END DESCRIPTION:
XS GIS Cut Line= 3
      1835625.01     13905475.00      1835825.00     13905525.00
      1836224.97     13905824.97
#Sta/Elev= 30
  4790.1 1982.52  4853.3 1978.03  4924.1 1975.58  4931.8 1959.81  4937.0 1960.52
  4944.7 1951.63  4955.0 1944.16  4973.1 1924.82  4978.2 1925.12  4985.9 1923.29
  5016.3 1922.81  5016.8 1922.31  5032.5 1922.81  5053.5 1927.20  5082.7 1927.53
  5103.5 1925.31  5120.8 1928.65  5174.4 1930.68  5182.7 1932.50  5189.0 1932.75
  5239.0 1941.46  5253.5 1945.24  5268.1 1947.82  5289.0 1950.13  5309.8 1953.87
  5318.1 1956.61  5374.4 1964.98  5403.5 1972.77  5468.1 1983.16  5496.2 1986.44
#Mann=5,-1,0
  4790.1    0.07       0  4853.3     0.1       0  5016.3    0.05       0
  5032.5     0.1       0  5120.8     0.1       0
Bank Sta=5016.3,5032.5
Exp/Cntr=0.3,0.1

Type RM Length L Ch R = 1,550,329,329,329
BEGIN DESCRIPTION:
Spur Branch 1.0
END DESCRIPTION:
XS GIS Cut Line= 3
      1835675.02     13905825.02      1835825.00     13905975.00
      1836075.03     13906075.01
#Sta/Elev= 30
  4787.9 1968.88  4816.2 1963.99  4844.4 1960.55  4858.6 1960.53  4886.9 1954.85
  4893.9 1952.13  4901.0 1951.58  4915.2 1948.50  4929.3 1944.59  4957.6 1933.48
  4971.7 1920.67  4985.9 1920.31  4988.3 1919.50  4988.8 1919.00  5004.6 1919.50
  5039.1 1922.71  5075.4 1924.22  5092.9 1926.79  5122.5 1928.11  5140.0 1932.30
  5146.8 1935.43  5152.1 1935.75  5161.6 1940.21  5176.4 1943.41  5183.1 1947.60
  5193.9 1951.11  5200.6 1955.14  5215.4 1960.37  5237.0 1970.94  5269.3 1973.97
#Mann=3,-1,0
  4787.9     0.1       0  4988.3    0.05       0  5004.6     0.1       0
Bank Sta=4988.3,5004.6
Exp/Cntr=0.3,0.1

Type RM Length L Ch R = 1,221,0,0,0
BEGIN DESCRIPTION:
Spur Branch 0.0
END DESCRIPTION:
XS GIS Cut Line= 4
      1835425.10     13905950.52      1835740.59     13906292.81
      1835997.88     13906327.95      1836231.22     13906223.10
#Sta/Elev= 30
  4449.3 1977.92  4495.1 1976.51  4657.8 1955.67  4763.9 1944.52  4784.9 1944.85
  4813.2 1940.49  4820.6 1937.87  4827.4 1937.62  4834.8 1934.81  4841.6 1934.45
  4863.1 1929.28  4877.0 1928.32  4905.1 1928.45  4914.8 1930.24  4929.4 1929.49
  4991.9 1916.36  4992.4 1915.86  5008.2 1916.36  5020.2 1917.00  5038.6 1921.57
  5080.7 1925.06  5110.9 1930.46  5115.9 1930.18  5121.1 1935.29  5131.2 1950.42
  5141.3 1969.29  5170.5 1972.18  5265.8 1977.00  5317.6 1977.51  5430.3 1981.73
#Mann=3,-1,0
  4449.3     0.1       0  4991.9    0.05       0  5008.2     0.1       0
Bank Sta=4991.9,5008.2
Exp/Cntr=0.3,0.1

Chan Stop Cuts=-1