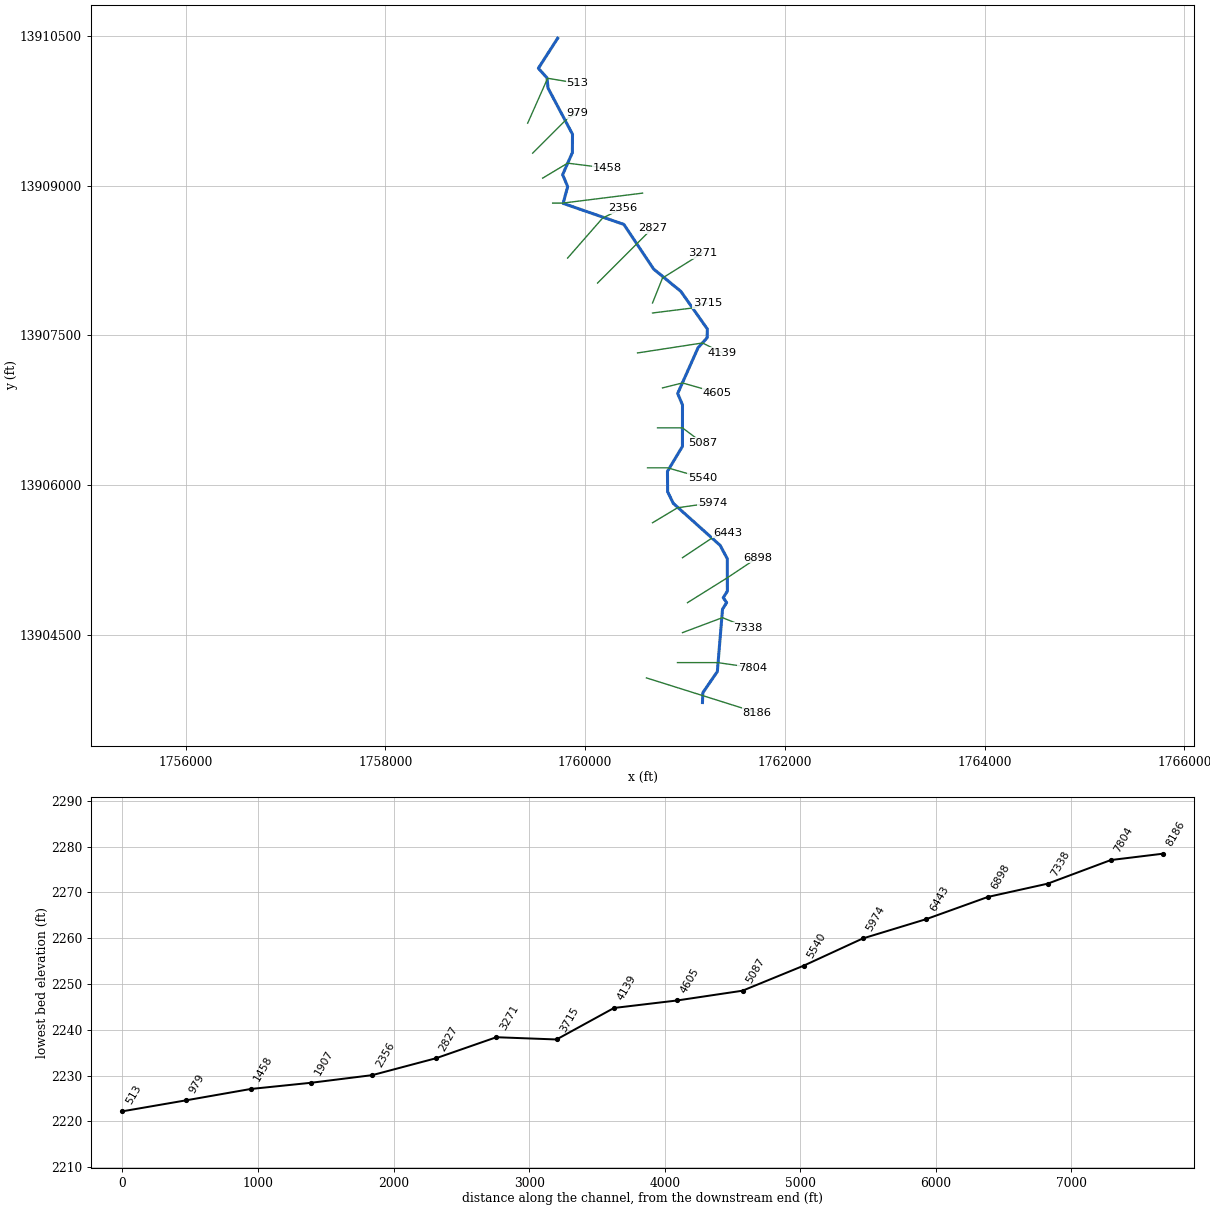
--- Stream0088.prj (project) ---

Proj Title=Stream0088 Base Level Engineering
Current Plan=p01
Default Exp/Contr=0.3,0.1
English Units
Geom File=g01
Flow File=f01
Plan File=p01
BEGIN DESCRIPTION:
Stream0088
END DESCRIPTION:

--- Stream0088.p01 (plan) ---

Plan Title=Multiple Run
Short Identifier=Multiple
Geom File=g01
Flow File=f01
Subcritical Flow
K Sum by GR= 0
Std Step Tol= 0.01
Critical Tol= 0.01
Num of Std Step Trials= 20
Max Error Tol= 0.3
Flow Tol Ratio= 0.001
Split Flow NTrial= 30
Split Flow Tol= 0.02
Split Flow Ratio= 0.02
Log Output Level= 0
Friction Slope Method= 1
Unsteady Friction Slope Method= 2
Unsteady Bridges Friction Slope Method= 1
Parabolic Critical Depth
Global Vel Dist=  1 , 1 , 1
Global Log Level= 0
CheckData=True
Encroach Param= -1, 0, 0, 0
BEGIN DESCRIPTION:
Multiple Run
END DESCRIPTION:

--- Stream0088.f01 (steady flow) ---

Flow Title=Multiple
Number of Profiles=7
Profile Names=10-year,25-year,50-year,1pct_min,100-year,1pct_plu,500-year
River Rch & RM= Stream0088,Reach-1,8186
    1567    2721    3833    2603    5194   10364    9443
Boundary for River Rch & Prof#=Stream0088,Reach-1,1
Up Type=0
Dn Type=3
Dn Slope=0.005
Boundary for River Rch & Prof#=Stream0088,Reach-1,2
Up Type=0
Dn Type=3
Dn Slope=0.005
Boundary for River Rch & Prof#=Stream0088,Reach-1,3
Up Type=0
Dn Type=3
Dn Slope=0.005
Boundary for River Rch & Prof#=Stream0088,Reach-1,4
Up Type=0
Dn Type=3
Dn Slope=0.005
Boundary for River Rch & Prof#=Stream0088,Reach-1,5
Up Type=0
Dn Type=3
Dn Slope=0.005
Boundary for River Rch & Prof#=Stream0088,Reach-1,6
Up Type=0
Dn Type=3
Dn Slope=0.005
Boundary for River Rch & Prof#=Stream0088,Reach-1,7
Up Type=0
Dn Type=3
Dn Slope=0.005

--- Stream0088.g01 (geometry) ---

Geom Title=Existing Conditions

River Reach=Stream0088,Reach-1
Reach XY= 30
      1761175.00     13903825.00      1761178.63     13903923.50
      1761323.95     13904135.44      1761375.65     13904759.84
      1761417.21     13904825.10      1761382.79     13904874.90
      1761424.35     13904940.16      1761423.80     13905264.50
      1761351.99     13905398.47      1760883.14     13905818.94
      1760826.20     13905935.50      1760824.56     13906140.18
      1760974.61     13906390.16      1760974.91     13906804.97
      1760926.80     13906918.89      1761130.85     13907377.29
      1761221.53     13907476.50      1761223.92     13907564.45
      1760958.36     13907941.71      1760685.78     13908165.32
      1760388.33     13908611.61      1759779.97     13908822.42
      1759825.70     13908990.06      1759775.09     13909109.61
      1759872.74     13909330.94      1759873.78     13909514.50
      1759628.83     13909976.59      1759619.45     13910077.43
      1759532.09     13910175.00      1759725.00     13910475.00

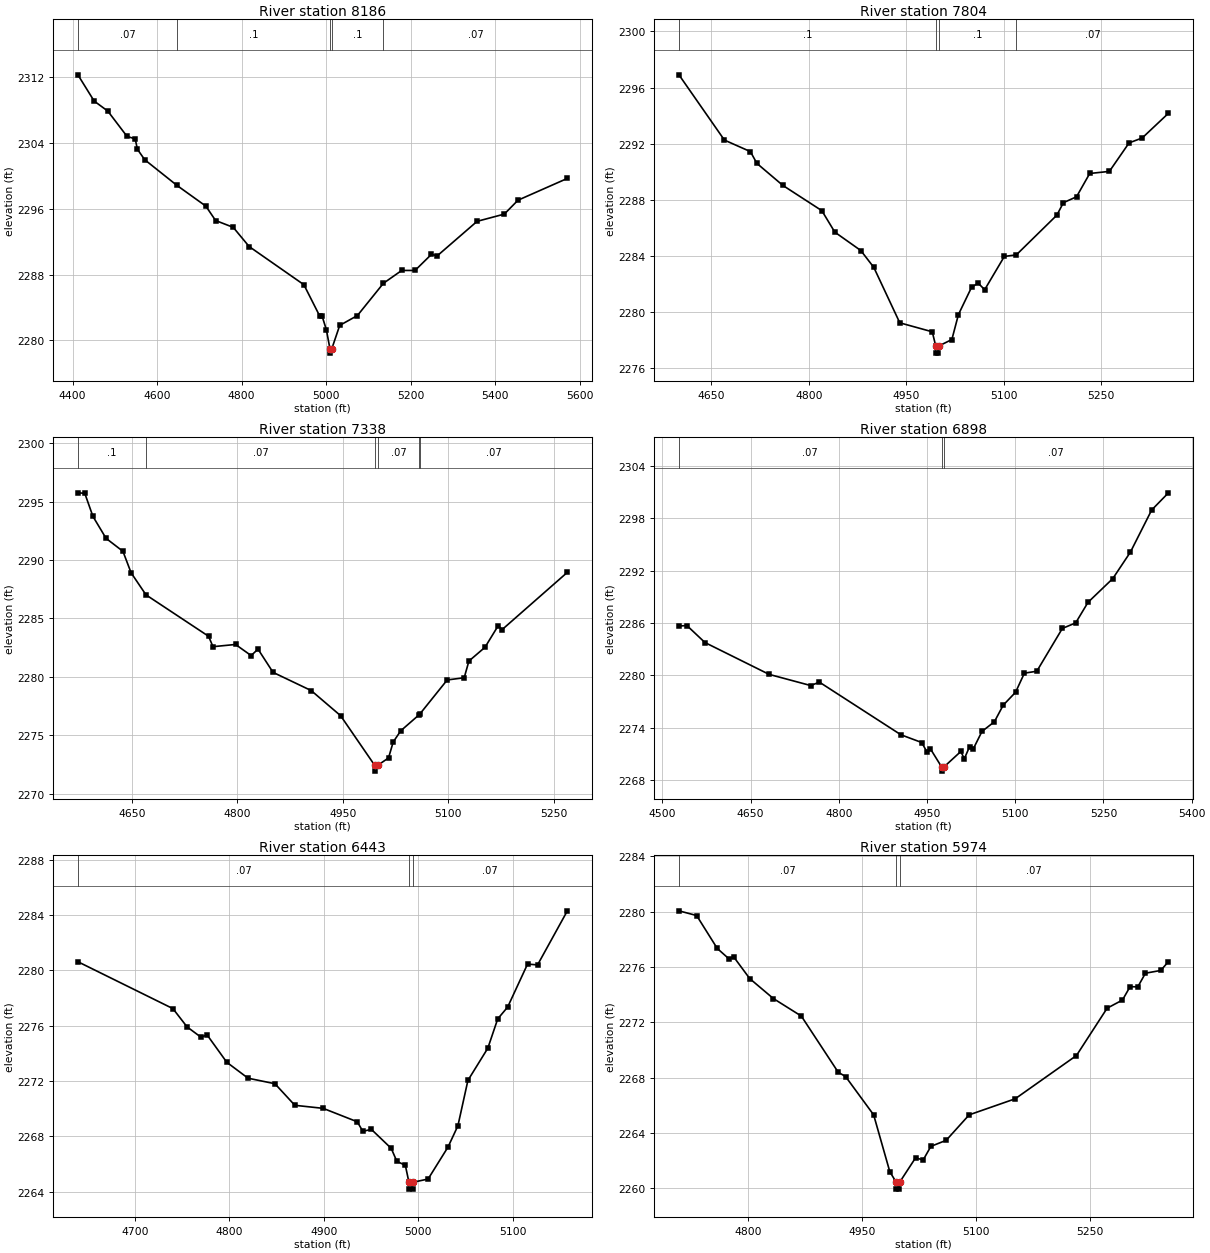
Type RM Length L Ch R = 1,8186,382,382,382
BEGIN DESCRIPTION:
Stream0088 18.0
END DESCRIPTION:
XS GIS Cut Line= 2
      1760614.21     13904071.83      1761718.77     13903724.10
#Sta/Elev= 30
  4412.7 2312.29  4451.2 2309.10  4483.5 2307.88  4528.9 2304.81  4548.3 2304.50
  4553.5 2303.24  4570.8 2301.97  4647.0 2298.85  4715.4 2296.33  4738.5 2294.58
  4780.2 2293.75  4817.8 2291.42  4947.3 2286.78  4984.9 2282.96  4990.2 2283.00
  5000.6 2281.29  5009.1 2278.96  5009.3 2278.46  5013.2 2278.96  5032.1 2281.83
  5074.0 2283.03  5135.5 2286.95  5178.8 2288.51  5210.3 2288.51  5249.2 2290.47
  5262.7 2290.28  5357.1 2294.48  5421.5 2295.36  5453.9 2297.05  5570.7 2299.70
#Mann=5,-1,0
  4412.7    0.07       0  4647.0     0.1       0  5009.1    0.05       0
  5013.2     0.1       0  5135.5    0.07       0
Bank Sta=5009.1,5013.2
Exp/Cntr=0.3,0.1

Type RM Length L Ch R = 1,7804,466,466,466
BEGIN DESCRIPTION:
Stream0088 17.0
END DESCRIPTION:
XS GIS Cut Line= 3
      1760924.98     13904225.00      1761325.00     13904225.00
      1761675.03     13904175.00
#Sta/Elev= 30
  4599.9 2296.91  4669.9 2292.26  4709.9 2291.44  4719.9 2290.60  4759.9 2289.03
  4819.9 2287.23  4839.9 2285.70  4879.9 2284.39  4899.9 2283.19  4939.9 2279.24
  4989.9 2278.60  4995.3 2277.58  4995.6 2277.08  4999.3 2277.08  4999.6 2277.58
  5020.1 2278.05  5030.2 2279.83  5050.4 2281.77  5060.5 2282.07  5070.6 2281.60
  5100.9 2283.97  5119.3 2284.08  5181.7 2286.91  5191.8 2287.80  5212.0 2288.22
  5232.3 2289.88  5262.6 2290.03  5292.9 2292.06  5313.1 2292.41  5353.5 2294.17
#Mann=4,-1,0
  4599.9     0.1       0  4995.3    0.05       0  4999.6     0.1       0
  5119.3    0.07       0
Bank Sta=4995.3,4999.6
Exp/Cntr=0.3,0.1

Type RM Length L Ch R = 1,7338,440,440,440
BEGIN DESCRIPTION:
Stream0088 16.0
END DESCRIPTION:
XS GIS Cut Line= 3
      1760975.00     13904525.00      1761375.00     13904675.00
      1761625.03     13904574.99
#Sta/Elev= 30
  4572.9 2295.76  4582.7 2295.72  4594.3 2293.74  4613.0 2291.86  4637.0 2290.75
  4648.6 2288.91  4669.8 2287.02  4758.9 2283.47  4765.1 2282.58  4797.2 2282.77
  4819.4 2281.82  4829.2 2282.37  4850.6 2280.38  4904.9 2278.82  4946.7 2276.67
  4995.2 2272.42  4995.5 2271.92  4999.6 2272.42  5014.9 2273.05  5021.6 2274.42
  5032.4 2275.38  5058.3 2276.74  5059.6 2276.82  5098.4 2279.73  5122.6 2279.92
  5129.3 2281.35  5152.2 2282.53  5171.1 2284.39  5176.5 2284.04  5269.4 2288.95
#Mann=6,-1,0
  4572.9     0.1       0  4669.8    0.07       0  4995.2    0.05       0
  4999.6    0.07       0  5058.3     0.1       0  5059.6    0.07       0
Bank Sta=4995.2,4999.6
Exp/Cntr=0.3,0.1

Type RM Length L Ch R = 1,6898,455,455,455
BEGIN DESCRIPTION:
Stream0088 15.0
END DESCRIPTION:
XS GIS Cut Line= 3
      1761025.03     13904825.02      1761425.00     13905075.00
      1761724.99     13905274.99
#Sta/Elev= 30
  4528.3 2285.66  4541.8 2285.72  4572.5 2283.77  4681.6 2280.12  4752.3 2278.84
  4767.1 2279.23  4905.6 2273.20  4941.0 2272.31  4949.8 2271.25  4955.7 2271.60
  4974.7 2269.53  4975.1 2269.03  4979.2 2269.53  5007.5 2271.28  5013.5 2270.45
  5022.5 2271.85  5028.5 2271.55  5043.5 2273.58  5064.6 2274.69  5079.6 2276.59
  5100.6 2278.07  5115.6 2280.26  5136.7 2280.48  5180.2 2285.39  5202.8 2286.02
  5223.8 2288.38  5265.9 2291.10  5295.9 2294.14  5332.0 2298.96  5360.5 2300.93
#Mann=3,-1,0
  4528.3    0.07       0  4974.7    0.05       0  4979.2    0.07       0
Bank Sta=4974.7,4979.2
Exp/Cntr=0.3,0.1

Type RM Length L Ch R = 1,6443,469,469,469
BEGIN DESCRIPTION:
Stream0088 14.0
END DESCRIPTION:
XS GIS Cut Line= 3
      1760974.99     13905274.99      1761275.00     13905475.00
      1761425.02     13905525.01
#Sta/Elev= 30
  4639.4 2280.62  4740.1 2277.23  4755.1 2275.91  4770.1 2275.15  4776.1 2275.35
  4797.2 2273.35  4819.7 2272.20  4848.2 2271.80  4869.3 2270.24  4899.3 2270.02
  4935.4 2269.05  4941.4 2268.36  4950.4 2268.50  4971.4 2267.13  4977.4 2266.19
  4986.4 2265.90  4990.2 2264.68  4990.5 2264.18  4994.4 2264.18  4994.7 2264.68
  5010.5 2264.91  5031.6 2267.22  5042.1 2268.76  5052.7 2272.04  5073.8 2274.37
  5084.3 2276.49  5094.8 2277.34  5115.9 2280.45  5126.5 2280.39  5158.1 2284.30
#Mann=3,-1,0
  4639.4    0.07       0  4990.2    0.05       0  4994.7    0.07       0
Bank Sta=4990.2,4994.7
Exp/Cntr=0.3,0.1

Type RM Length L Ch R = 1,5974,434,434,434
BEGIN DESCRIPTION:
Stream0088 13.0
END DESCRIPTION:
XS GIS Cut Line= 3
      1760675.00     13905625.00      1760925.00     13905775.00
      1761274.99     13905825.00
#Sta/Elev= 30
  4708.7 2280.07  4732.0 2279.73  4759.2 2277.35  4774.8 2276.59  4780.6 2276.76
  4802.0 2275.17  4833.1 2273.73  4870.0 2272.46  4918.6 2268.40  4928.3 2268.09
  4965.3 2265.32  4986.6 2261.21  4995.0 2260.45  4995.4 2259.95  4999.3 2259.95
  4999.6 2260.45  5020.5 2262.21  5030.6 2262.06  5040.7 2263.04  5060.9 2263.48
  5091.2 2265.32  5151.8 2266.48  5232.6 2269.61  5273.0 2273.03  5293.2 2273.62
  5303.3 2274.59  5313.4 2274.57  5323.5 2275.56  5343.7 2275.76  5353.8 2276.40
#Mann=3,-1,0
  4708.7    0.07       0  4995.0    0.05       0  4999.6    0.07       0
Bank Sta=4995,4999.6
Exp/Cntr=0.3,0.1

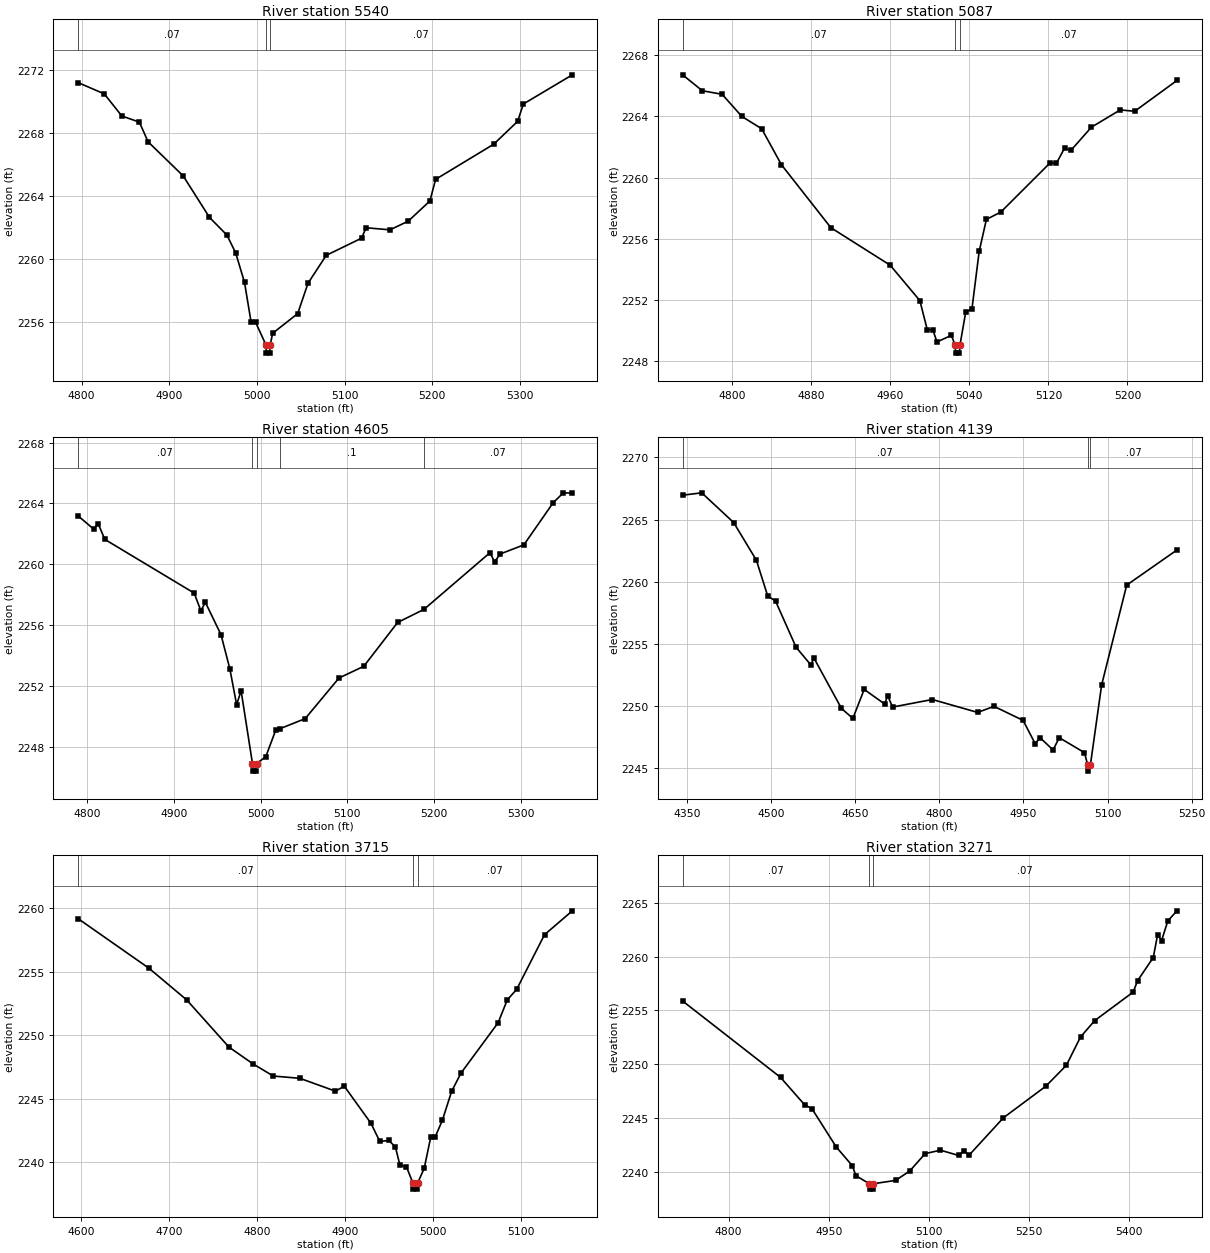
Type RM Length L Ch R = 1,5540,453,453,453
BEGIN DESCRIPTION:
Stream0088 12.0
END DESCRIPTION:
XS GIS Cut Line= 3
      1760625.02     13906175.00      1760825.00     13906175.00
      1761175.01     13906075.00
#Sta/Elev= 30
  4795.9 2271.19  4825.9 2270.47  4845.9 2269.07  4865.9 2268.68  4875.9 2267.43
  4915.9 2265.27  4945.9 2262.64  4965.9 2261.51  4975.9 2260.37  4985.9 2258.51
  4993.4 2255.99  4998.5 2255.99  5010.5 2254.53  5010.8 2254.03  5014.8 2254.03
  5015.1 2254.53  5018.0 2255.29  5046.6 2256.54  5058.3 2258.46  5079.1 2260.23
  5119.4 2261.32  5124.6 2261.98  5151.9 2261.85  5172.7 2262.40  5197.4 2263.68
  5203.9 2265.05  5270.2 2267.28  5297.5 2268.73  5304.0 2269.83  5359.9 2271.68
#Mann=3,-1,0
  4795.9    0.07       0  5010.5    0.05       0  5015.1    0.07       0
Bank Sta=5010.5,5015.1
Exp/Cntr=0.3,0.1

Type RM Length L Ch R = 1,5087,482,482,482
BEGIN DESCRIPTION:
Stream0088 11.0
END DESCRIPTION:
XS GIS Cut Line= 3
      1760725.01     13906575.00      1760975.00     13906575.00
      1761175.01     13906424.99
#Sta/Elev= 30
  4750.0 2266.71  4770.0 2265.67  4790.0 2265.44  4810.0 2263.99  4830.0 2263.19
  4850.0 2260.84  4900.0 2256.73  4960.0 2254.28  4990.0 2251.97  4997.5 2250.07
  5003.1 2250.07  5007.3 2249.27  5021.9 2249.70  5025.8 2249.04  5026.1 2248.54
  5030.1 2248.54  5030.5 2249.04  5036.4 2251.22  5042.7 2251.43  5050.0 2255.18
  5057.3 2257.27  5071.9 2257.75  5121.9 2260.97  5128.1 2260.93  5136.4 2261.93
  5142.7 2261.77  5163.5 2263.29  5192.7 2264.42  5207.3 2264.33  5250.0 2266.34
#Mann=3,-1,0
  4750.0    0.07       0  5025.8    0.05       0  5030.5    0.07       0
Bank Sta=5025.8,5030.5
Exp/Cntr=0.3,0.1

Type RM Length L Ch R = 1,4605,466,466,466
BEGIN DESCRIPTION:
Stream0088 10.0
END DESCRIPTION:
XS GIS Cut Line= 3
      1760775.02     13906975.00      1760975.00     13907025.00
      1761324.96     13906925.01
#Sta/Elev= 30
  4789.3 2263.19  4807.3 2262.32  4812.5 2262.68  4820.2 2261.64  4923.3 2258.11
  4931.0 2256.95  4936.2 2257.50  4954.2 2255.38  4964.5 2253.11  4972.2 2250.78
  4977.4 2251.69  4990.5 2246.91  4990.8 2246.41  4994.9 2246.41  4995.2 2246.91
  5005.8 2247.35  5017.5 2249.13  5022.3 2249.20  5051.3 2249.86  5090.3 2252.53
  5118.9 2253.30  5157.9 2256.18  5188.3 2257.04  5264.5 2260.77  5269.7 2260.16
  5276.2 2260.68  5303.5 2261.28  5337.3 2264.05  5349.0 2264.70  5359.4 2264.68
#Mann=5,-1,0
  4789.3    0.07       0  4990.5    0.05       0  4995.2    0.07       0
  5022.3     0.1       0  5188.3    0.07       0
Bank Sta=4990.5,4995.2
Exp/Cntr=0.3,0.1

Type RM Length L Ch R = 1,4139,424,424,424
BEGIN DESCRIPTION:
Stream0088 9.0
END DESCRIPTION:
XS GIS Cut Line= 3
      1760524.98     13907325.00      1761175.00     13907425.00
      1761375.02     13907324.99
#Sta/Elev= 30
  4342.3 2266.96  4376.5 2267.15  4433.4 2264.76  4473.9 2261.73  4494.1 2258.85
  4508.0 2258.45  4544.7 2254.73  4571.2 2253.30  4576.3 2253.88  4625.6 2249.81
  4645.9 2249.01  4666.1 2251.34  4702.8 2250.16  4707.8 2250.85  4716.7 2249.92
  4787.5 2250.53  4868.4 2249.49  4897.5 2249.98  4949.4 2248.85  4970.9 2246.98
  4979.7 2247.46  5002.8 2246.47  5013.9 2247.46  5058.7 2246.26  5064.6 2245.27
  5065.0 2244.77  5069.4 2245.27  5089.4 2251.70  5134.1 2259.73  5223.6 2262.55
#Mann=3,-1,0
  4342.3    0.07       0  5064.6    0.05       0  5069.4    0.07       0
Bank Sta=5064.6,5069.4
Exp/Cntr=0.3,0.1

Type RM Length L Ch R = 1,3715,444,444,444
BEGIN DESCRIPTION:
Stream0088 8.0
END DESCRIPTION:
XS GIS Cut Line= 3
      1760675.02     13907725.00      1761075.00     13907775.00
      1761224.99     13907825.00
#Sta/Elev= 30
  4596.9 2259.18  4677.5 2255.27  4720.3 2252.78  4768.2 2249.07  4795.9 2247.73
  4818.6 2246.79  4848.8 2246.61  4889.1 2245.60  4899.2 2245.99  4929.5 2243.07
  4939.5 2241.64  4949.6 2241.72  4957.2 2241.22  4962.2 2239.82  4969.8 2239.64
  4977.0 2238.39  4977.5 2237.89  4982.2 2237.89  4982.6 2238.39  4989.9 2239.52
  4997.5 2242.03  5002.6 2242.03  5010.5 2243.30  5021.1 2245.59  5031.6 2247.01
  5073.8 2250.98  5084.3 2252.79  5094.9 2253.61  5126.5 2257.91  5158.1 2259.79
#Mann=3,-1,0
  4596.9    0.07       0  4977.0    0.05       0  4982.6    0.07       0
Bank Sta=4977,4982.6
Exp/Cntr=0.3,0.1

Type RM Length L Ch R = 1,3271,444,444,444
BEGIN DESCRIPTION:
Stream0088 7.0
END DESCRIPTION:
XS GIS Cut Line= 3
      1760674.99     13907824.99      1760775.00     13908075.00
      1761175.02     13908325.02
#Sta/Elev= 30
  4731.0 2255.87  4877.8 2248.77  4914.1 2246.21  4924.9 2245.86  4961.2 2242.31
  4985.5 2240.55  4990.8 2239.63  5011.0 2238.88  5011.4 2238.38  5016.2 2238.38
  5016.7 2238.88  5050.4 2239.19  5071.6 2240.07  5094.6 2241.68  5117.6 2242.00
  5144.7 2241.51  5153.6 2241.95  5160.1 2241.51  5211.9 2245.01  5275.6 2247.95
  5306.3 2249.89  5327.5 2252.52  5348.7 2254.04  5406.5 2256.70  5413.0 2257.75
  5436.6 2259.91  5443.1 2262.04  5449.0 2261.48  5458.4 2263.31  5472.0 2264.25
#Mann=3,-1,0
  4731.0    0.07       0  5011.0    0.05       0  5016.7    0.07       0
Bank Sta=5011,5016.7
Exp/Cntr=0.3,0.1

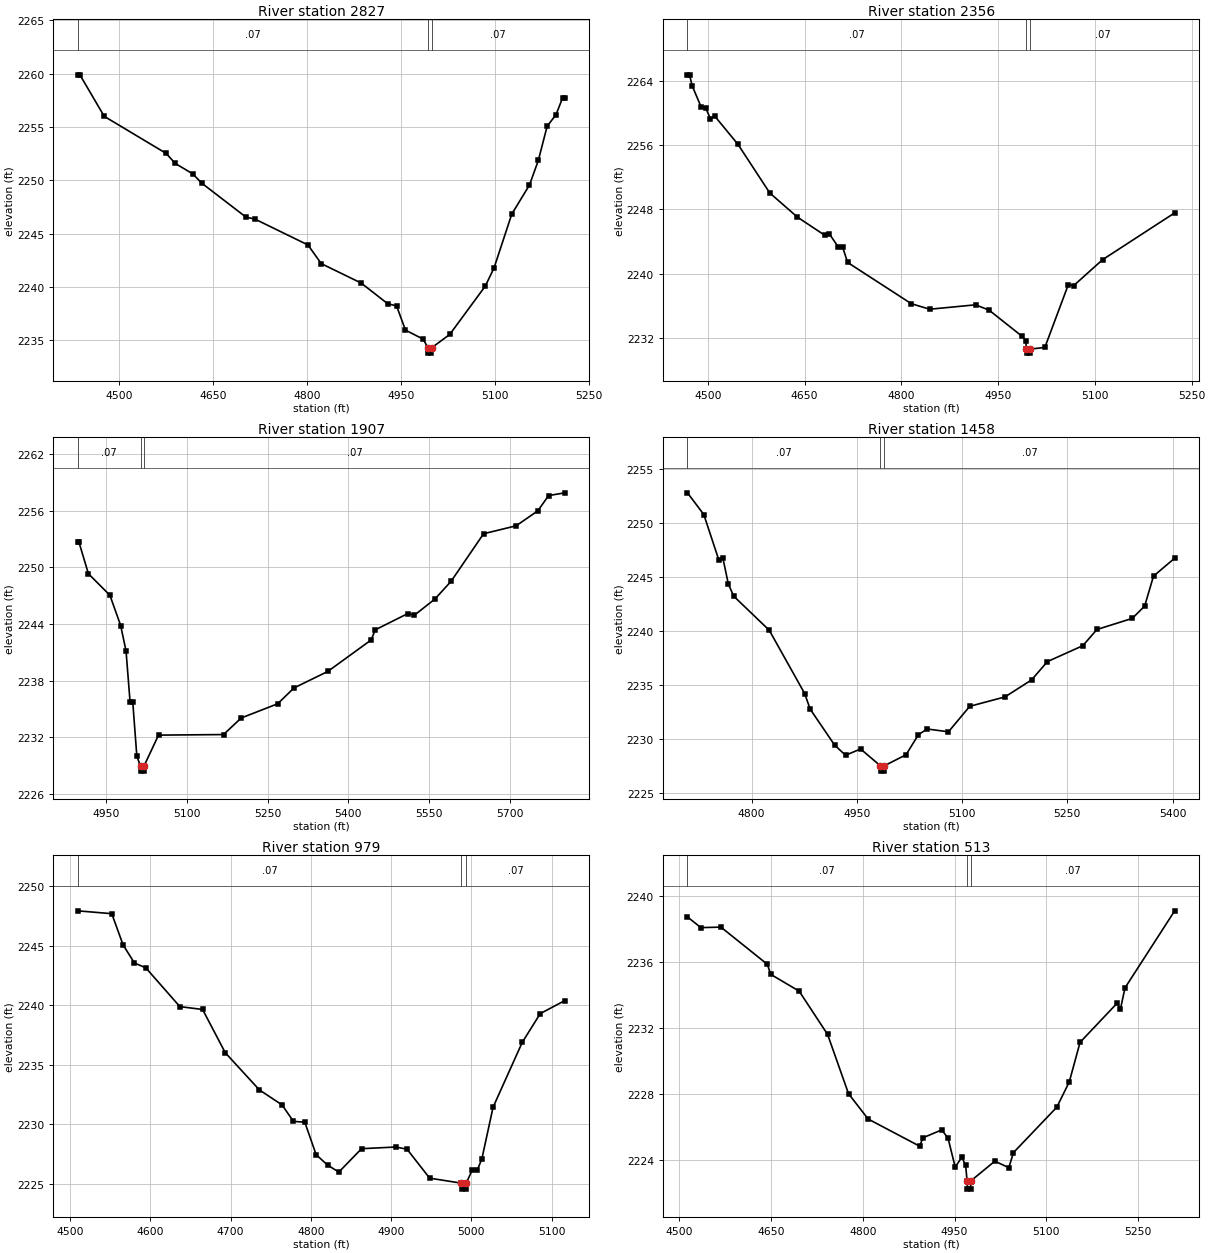
Type RM Length L Ch R = 1,2827,471,471,471
BEGIN DESCRIPTION:
Stream0088 6.0
END DESCRIPTION:
XS GIS Cut Line= 3
      1760124.99     13908024.99      1760525.00     13908425.00
      1760674.98     13908574.98
#Sta/Elev= 30
  4434.3 2259.89  4437.9 2259.89  4476.7 2256.00  4575.7 2252.52  4589.9 2251.59
  4618.2 2250.60  4632.3 2249.74  4703.0 2246.55  4717.2 2246.37  4802.0 2243.94
  4823.2 2242.19  4886.9 2240.37  4929.3 2238.43  4943.4 2238.23  4957.6 2235.96
  4985.9 2235.11  4993.6 2234.30  4994.1 2233.80  4998.9 2233.80  4999.4 2234.30
  5028.3 2235.55  5084.9 2240.07  5099.0 2241.78  5127.3 2246.83  5155.6 2249.56
  5169.7 2251.86  5183.8 2255.07  5198.0 2256.16  5208.6 2257.75  5212.1 2257.75
#Mann=3,-1,0
  4434.3    0.07       0  4993.6    0.05       0  4999.4    0.07       0
Bank Sta=4993.6,4999.4
Exp/Cntr=0.3,0.1

Type RM Length L Ch R = 1,2356,449,449,449
BEGIN DESCRIPTION:
Stream0088 5.0
END DESCRIPTION:
XS GIS Cut Line= 3
      1759825.00     13908275.01      1760175.00     13908675.00
      1760374.99     13908775.00
#Sta/Elev= 30
  4468.5 2264.72  4471.8 2264.72  4475.6 2263.39  4489.8 2260.70  4496.5 2260.64
  4504.1 2259.25  4510.7 2259.59  4546.8 2256.07  4596.1 2250.02  4638.9 2247.02
  4681.1 2244.77  4688.2 2244.96  4702.5 2243.27  4709.1 2243.25  4716.7 2241.38
  4815.4 2236.25  4843.9 2235.56  4915.1 2236.11  4935.9 2235.45  4986.2 2232.25
  4992.9 2231.64  4993.8 2230.60  4994.2 2230.10  4999.1 2230.10  4999.6 2230.60
  5022.4 2230.81  5058.7 2238.61  5067.1 2238.50  5111.8 2241.72  5223.6 2247.55
#Mann=3,-1,0
  4468.5    0.07       0  4993.8    0.05       0  4999.6    0.07       0
Bank Sta=4993.8,4999.6
Exp/Cntr=0.3,0.1

Type RM Length L Ch R = 1,1907,449,449,449
BEGIN DESCRIPTION:
Stream0088 4.0
END DESCRIPTION:
XS GIS Cut Line= 3
      1759675.02     13908825.00      1759775.00     13908825.00
      1760575.00     13908925.00
#Sta/Elev= 30
  4896.5 2252.66  4899.0 2252.66  4916.5 2249.33  4956.5 2247.05  4976.5 2243.85
  4986.5 2241.15  4994.0 2235.76  4999.0 2235.76  5006.6 2230.00  5013.7 2228.94
  5014.2 2228.44  5019.1 2228.44  5019.6 2228.94  5046.9 2232.25  5167.8 2232.31
  5200.6 2234.06  5268.6 2235.57  5298.8 2237.24  5361.8 2238.99  5442.4 2242.32
  5450.0 2243.39  5510.4 2245.11  5523.0 2244.95  5560.8 2246.64  5591.1 2248.53
  5651.5 2253.56  5712.0 2254.40  5752.3 2255.98  5772.5 2257.60  5802.7 2257.89
#Mann=3,-1,0
  4896.5    0.07       0  5013.7    0.05       0  5019.6    0.07       0
Bank Sta=5013.7,5019.6
Exp/Cntr=0.3,0.1

Type RM Length L Ch R = 1,1458,479,479,479
BEGIN DESCRIPTION:
Stream0088 3.0
END DESCRIPTION:
XS GIS Cut Line= 3
      1759575.04     13909075.02      1759825.00     13909225.00
      1760224.98     13909175.00
#Sta/Elev= 30
  4708.5 2252.83  4731.8 2250.82  4753.2 2246.62  4759.0 2246.79  4766.8 2244.38
  4774.5 2243.26  4825.1 2240.11  4875.6 2234.25  4883.4 2232.81  4918.4 2229.47
  4933.9 2228.54  4955.3 2229.12  4983.4 2227.57  4983.9 2227.07  4988.8 2227.07
  4989.3 2227.57  5020.2 2228.59  5037.8 2230.45  5050.4 2230.97  5080.6 2230.71
  5110.9 2233.07  5161.2 2233.94  5199.0 2235.51  5221.7 2237.21  5272.1 2238.68
  5292.3 2240.18  5342.7 2241.21  5360.3 2242.35  5372.9 2245.12  5403.1 2246.78
#Mann=3,-1,0
  4708.5    0.07       0  4983.4    0.05       0  4989.3    0.07       0
Bank Sta=4983.4,4989.3
Exp/Cntr=0.3,0.1

Type RM Length L Ch R = 1,979,466,466,466
BEGIN DESCRIPTION:
Stream0088 2.0
END DESCRIPTION:
XS GIS Cut Line= 3
      1759474.98     13909324.98      1759825.00     13909675.00
      1759924.99     13909725.00
#Sta/Elev= 30
  4509.6 2247.91  4552.1 2247.67  4566.2 2245.05  4580.3 2243.54  4594.5 2243.13
  4636.9 2239.88  4665.2 2239.64  4693.5 2236.01  4735.9 2232.90  4764.2 2231.64
  4778.3 2230.26  4792.5 2230.19  4806.6 2227.47  4820.8 2226.60  4834.9 2226.01
  4863.2 2227.97  4905.6 2228.11  4919.8 2227.93  4948.0 2225.50  4987.5 2225.08
  4988.0 2224.58  4993.0 2224.58  4993.5 2225.08  5001.1 2226.19  5007.4 2226.19
  5013.0 2227.11  5027.0 2231.45  5063.3 2236.88  5085.7 2239.29  5116.4 2240.39
#Mann=3,-1,0
  4509.6    0.07       0  4987.5    0.05       0  4993.5    0.07       0
Bank Sta=4987.5,4993.5
Exp/Cntr=0.3,0.1

Type RM Length L Ch R = 1,513,0,0,0
BEGIN DESCRIPTION:
Stream0088 1.0
END DESCRIPTION:
XS GIS Cut Line= 3
      1759425.01     13909625.03      1759625.00     13910075.00
      1759925.05     13910024.99
#Sta/Elev= 30
  4513.4 2238.74  4535.3 2238.09  4568.1 2238.12  4644.0 2235.86  4649.5 2235.25
  4696.0 2234.23  4742.5 2231.60  4776.7 2228.00  4808.8 2226.46  4893.0 2224.81
  4898.4 2225.32  4929.2 2225.80  4939.5 2225.29  4951.1 2223.54  4962.0 2224.14
  4968.2 2223.64  4970.6 2222.70  4971.1 2222.20  4976.2 2222.20  4976.7 2222.70
  5016.0 2223.90  5038.8 2223.50  5046.4 2224.42  5117.3 2227.18  5137.6 2228.71
  5155.3 2231.12  5216.2 2233.51  5221.2 2233.12  5228.8 2234.43  5310.0 2239.11
#Mann=3,-1,0
  4513.4    0.07       0  4970.6    0.05       0  4976.7    0.07       0
Bank Sta=4970.6,4976.7
Exp/Cntr=0.3,0.1

Chan Stop Cuts=-1