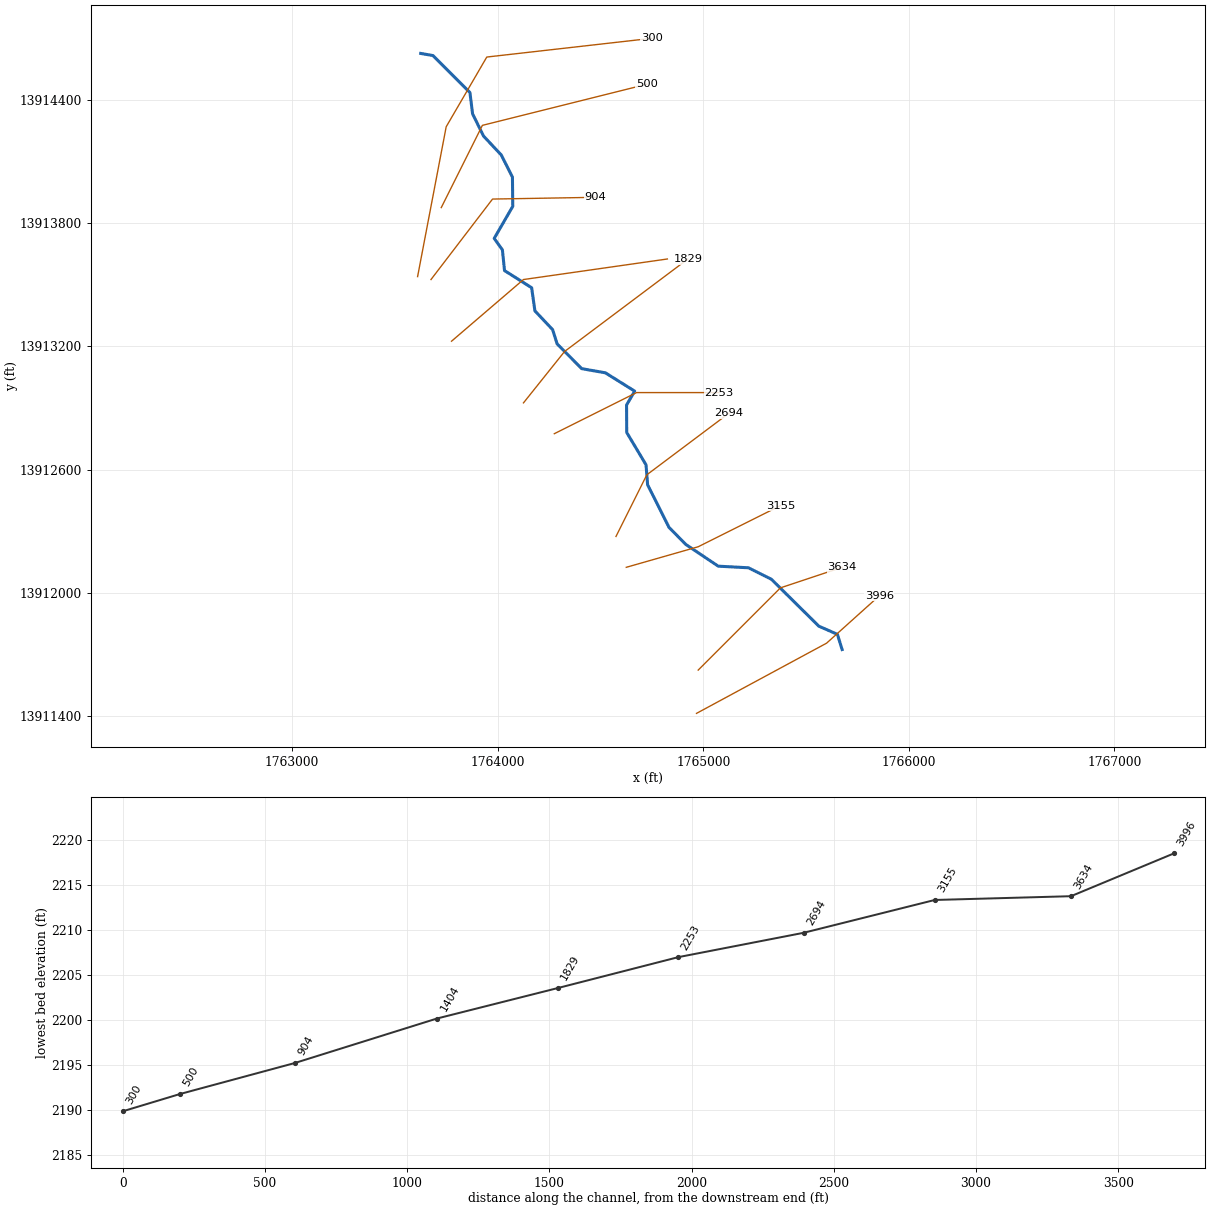
--- Stream0089.prj (project) ---

Proj Title=Stream0089 Base Level Engineering
Current Plan=p01
Default Exp/Contr=0.3,0.1
English Units
Geom File=g01
Flow File=f01
Plan File=p01
BEGIN DESCRIPTION:
Stream0089
END DESCRIPTION:

--- Stream0089.p01 (plan) ---

Plan Title=Multiple Run
Short Identifier=Multiple
Geom File=g01
Flow File=f01
Subcritical Flow
K Sum by GR= 0
Std Step Tol= 0.01
Critical Tol= 0.01
Num of Std Step Trials= 20
Max Error Tol= 0.3
Flow Tol Ratio= 0.001
Split Flow NTrial= 30
Split Flow Tol= 0.02
Split Flow Ratio= 0.02
Log Output Level= 0
Friction Slope Method= 1
Unsteady Friction Slope Method= 2
Unsteady Bridges Friction Slope Method= 1
Parabolic Critical Depth
Global Vel Dist=  1 , 1 , 1
Global Log Level= 0
CheckData=True
Encroach Param= -1, 0, 0, 0
BEGIN DESCRIPTION:
Multiple Run
END DESCRIPTION:

--- Stream0089.f01 (steady flow) ---

Flow Title=Multiple
Number of Profiles=7
Profile Names=10-year,25-year,50-year,1pct_min,100-year,1pct_plu,500-year
River Rch & RM= Stream0089,Reach-1,3996
    1189    2036    2841    1913    3817    7615    6817
Boundary for River Rch & Prof#=Stream0089,Reach-1,1
Up Type=0
Dn Type=3
Dn Slope=0.005
Boundary for River Rch & Prof#=Stream0089,Reach-1,2
Up Type=0
Dn Type=3
Dn Slope=0.005
Boundary for River Rch & Prof#=Stream0089,Reach-1,3
Up Type=0
Dn Type=3
Dn Slope=0.005
Boundary for River Rch & Prof#=Stream0089,Reach-1,4
Up Type=0
Dn Type=3
Dn Slope=0.005
Boundary for River Rch & Prof#=Stream0089,Reach-1,5
Up Type=0
Dn Type=3
Dn Slope=0.005
Boundary for River Rch & Prof#=Stream0089,Reach-1,6
Up Type=0
Dn Type=3
Dn Slope=0.005
Boundary for River Rch & Prof#=Stream0089,Reach-1,7
Up Type=0
Dn Type=3
Dn Slope=0.005

--- Stream0089.g01 (geometry) ---

Geom Title=Existing Conditions

River Reach=Stream0089,Reach-1
Reach XY= 30
      1765675.00     13911725.00      1765652.18     13911798.98
      1765561.80     13911838.63      1765331.06     13912066.86
      1765219.07     13912122.75      1765072.56     13912130.48
      1764915.30     13912235.77      1764833.13     13912318.93
      1764728.83     13912526.58      1764721.17     13912623.42
      1764627.23     13912780.93      1764626.38     13912914.57
      1764665.99     13912982.02      1764523.42     13913071.17
      1764408.25     13913091.46      1764288.63     13913211.79
      1764266.82     13913281.04      1764180.54     13913372.58
      1764164.61     13913485.10      1764032.74     13913568.55
      1764022.44     13913669.10      1763982.53     13913725.01
      1764072.77     13913880.93      1764071.26     13914023.44
      1764016.84     13914131.05      1763930.84     13914222.71
      1763877.33     13914330.97      1763864.48     13914434.79
      1763684.79     13914614.49      1763625.00     13914625.00

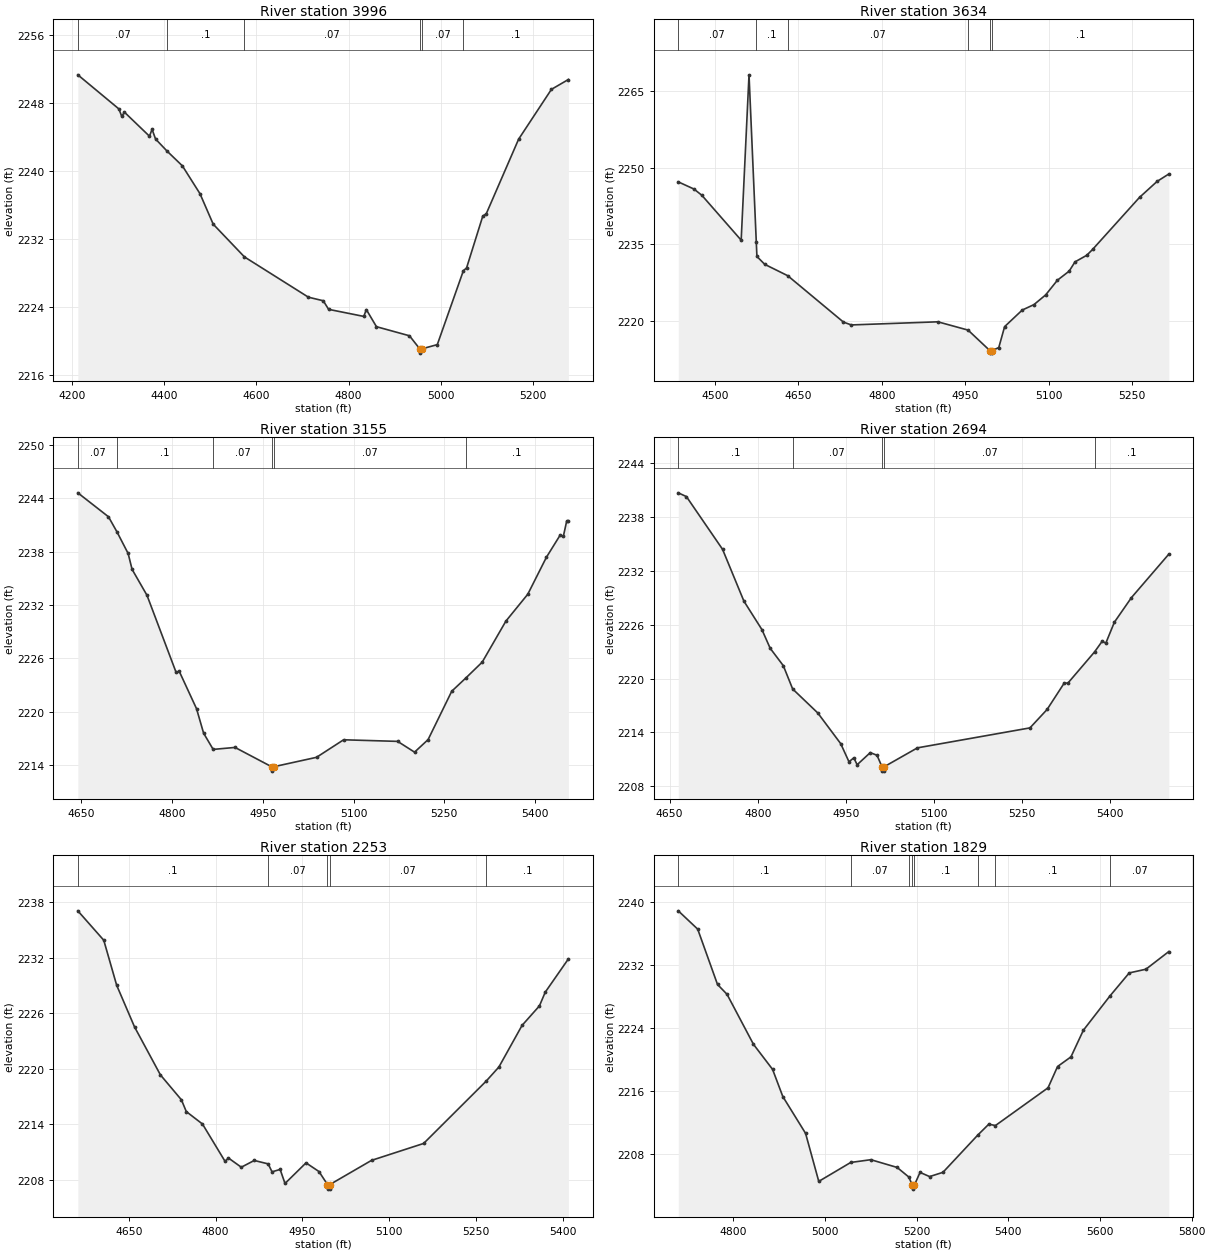
Type RM Length L Ch R = 1,3996,362,362,362
BEGIN DESCRIPTION:
Stream0089 9.0
END DESCRIPTION:
XS GIS Cut Line= 3
      1764966.72     13911414.40      1765599.43     13911755.88
      1765855.69     13911986.15
#Sta/Elev= 30
  4213.2 2251.27  4302.2 2247.26  4308.5 2246.38  4314.2 2246.88  4368.5 2244.05
  4374.2 2244.86  4381.7 2243.72  4406.8 2242.29  4439.9 2240.56  4478.0 2237.29
  4506.7 2233.70  4574.4 2229.85  4713.1 2225.11  4745.3 2224.69  4756.9 2223.68
  4833.1 2222.85  4838.7 2223.65  4860.6 2221.64  4932.2 2220.57  4954.5 2219.03
  4954.8 2218.53  4958.6 2219.03  4992.5 2219.53  5049.0 2228.22  5056.0 2228.56
  5091.1 2234.65  5098.6 2234.92  5168.8 2243.70  5239.9 2249.56  5276.7 2250.72
#Mann=6,-1,0
  4213.2    0.07       0  4406.8     0.1       0  4574.4    0.07       0
  4954.5    0.05       0  4958.6    0.07       0  5049.0     0.1       0
Bank Sta=4954.5,4958.6
Exp/Cntr=0.3,0.1

Type RM Length L Ch R = 1,3634,479,479,479
BEGIN DESCRIPTION:
Stream0089 8.0
END DESCRIPTION:
XS GIS Cut Line= 3
      1764975.02     13911625.02      1765375.00     13912025.00
      1765675.02     13912125.01
#Sta/Elev= 30
  4434.1 2247.24  4462.3 2245.84  4476.5 2244.62  4547.2 2235.84  4561.3 2268.16
  4574.4 2235.41  4575.5 2232.66  4589.6 2231.12  4630.9 2228.90  4731.1 2219.83
  4745.2 2219.28  4900.8 2219.89  4955.1 2218.27  4994.2 2214.27  4994.4 2213.77
  4998.0 2213.77  4998.3 2214.27  5010.3 2214.86  5020.8 2218.95  5052.5 2222.19
  5073.5 2223.25  5094.6 2225.15  5115.7 2228.02  5136.8 2229.79  5147.3 2231.60
  5168.4 2232.89  5178.9 2234.03  5263.3 2244.21  5294.9 2247.33  5316.0 2248.78
#Mann=6,-1,0
  4434.1    0.07       0  4574.4     0.1       0  4630.9    0.07       0
  4955.1     0.1       0  4994.2    0.05       0  4998.3     0.1       0
Bank Sta=4994.2,4998.3
Exp/Cntr=0.3,0.1

Type RM Length L Ch R = 1,3155,461,461,461
BEGIN DESCRIPTION:
Stream0089 7.0
END DESCRIPTION:
XS GIS Cut Line= 3
      1764625.02     13912125.00      1764975.00     13912225.00
      1765375.00     13912425.00
#Sta/Elev= 30
  4644.0 2244.60  4694.7 2241.91  4708.7 2240.22  4727.2 2237.79  4733.7 2236.01
  4758.4 2233.09  4806.5 2224.44  4811.7 2224.56  4840.3 2220.36  4852.0 2217.61
  4867.8 2215.79  4904.0 2216.01  4964.3 2213.85  4964.6 2213.35  4968.4 2213.85
  5038.7 2214.90  5083.5 2216.87  5172.9 2216.69  5200.8 2215.48  5223.2 2216.89
  5262.3 2222.32  5285.8 2223.82  5312.7 2225.59  5351.8 2230.19  5388.1 2233.22
  5418.9 2237.37  5441.2 2239.81  5446.8 2239.70  5452.4 2241.43  5455.2 2241.43
#Mann=6,-1,0
  4644.0    0.07       0  4708.7     0.1       0  4867.8    0.07       0
  4964.3    0.05       0  4968.4    0.07       0  5285.8     0.1       0
Bank Sta=4964.3,4968.4
Exp/Cntr=0.3,0.1

Type RM Length L Ch R = 1,2694,441,441,441
BEGIN DESCRIPTION:
Stream0089 6.0
END DESCRIPTION:
XS GIS Cut Line= 3
      1764575.01     13912275.03      1764725.00     13912575.00
      1765125.02     13912875.01
#Sta/Elev= 30
  4664.6 2240.66  4678.5 2240.24  4740.0 2234.38  4776.4 2228.61  4807.1 2225.44
  4821.1 2223.37  4843.5 2221.43  4859.4 2218.84  4902.2 2216.17  4941.3 2212.75
  4955.3 2210.74  4963.6 2211.18  4969.2 2210.41  4991.6 2211.76  5003.1 2211.46
  5011.4 2210.20  5011.7 2209.70  5015.3 2209.70  5015.6 2210.20  5071.9 2212.29
  5263.5 2214.51  5292.7 2216.56  5321.9 2219.50  5328.1 2219.49  5373.5 2222.96
  5386.4 2224.14  5392.7 2223.94  5407.3 2226.27  5436.4 2229.01  5500.0 2233.84
#Mann=5,-1,0
  4664.6     0.1       0  4859.4    0.07       0  5011.4    0.05       0
  5015.6    0.07       0  5373.5     0.1       0
Bank Sta=5011.4,5015.6
Exp/Cntr=0.3,0.1

Type RM Length L Ch R = 1,2253,424,424,424
BEGIN DESCRIPTION:
Stream0089 5.0
END DESCRIPTION:
XS GIS Cut Line= 3
      1764274.97     13912774.99      1764675.00     13912975.00
      1765074.96     13912975.00
#Sta/Elev= 30
  4562.0 2237.09  4606.8 2233.91  4629.1 2229.04  4659.9 2224.54  4704.6 2219.35
  4740.9 2216.65  4749.3 2215.38  4777.3 2214.03  4816.4 2209.98  4822.0 2210.36
  4844.3 2209.36  4866.7 2210.09  4890.7 2209.72  4897.4 2208.86  4911.4 2209.12
  4919.8 2207.60  4956.1 2209.83  4978.5 2208.89  4993.1 2207.49  4993.4 2206.99
  4997.1 2206.99  4997.4 2207.49  5069.2 2210.10  5159.2 2211.93  5267.2 2218.67
  5289.2 2220.20  5329.2 2224.70  5359.2 2226.81  5369.2 2228.29  5409.2 2231.89
#Mann=5,-1,0
  4562.0     0.1       0  4890.7    0.07       0  4993.1    0.05       0
  4997.4    0.07       0  5267.2     0.1       0
Bank Sta=4993.1,4997.4
Exp/Cntr=0.3,0.1

Type RM Length L Ch R = 1,1829,425,425,425
BEGIN DESCRIPTION:
Stream0089 4.0
END DESCRIPTION:
XS GIS Cut Line= 3
      1764125.02     13912925.02      1764325.00     13913175.00
      1764924.97     13913624.98
#Sta/Elev= 30
  4680.1 2238.82  4722.5 2236.50  4765.7 2229.49  4786.5 2228.24  4844.2 2221.90
  4885.8 2218.73  4908.2 2215.28  4957.8 2210.62  4986.6 2204.53  5056.3 2206.93
  5100.2 2207.28  5157.5 2206.30  5182.9 2205.09  5190.8 2204.05  5191.1 2203.55
  5195.1 2204.05  5207.5 2205.67  5228.4 2205.14  5257.5 2205.68  5333.6 2210.41
  5357.5 2211.78  5372.0 2211.61  5486.7 2216.39  5507.5 2219.09  5536.7 2220.31
  5563.8 2223.69  5621.9 2228.04  5663.8 2230.95  5700.2 2231.42  5750.2 2233.66
#Mann=8,-1,0
  4680.1     0.1       0  5056.3    0.07       0  5182.9     0.1       0
  5190.8    0.05       0  5195.1     0.1       0  5333.6    0.07       0
  5372.0     0.1       0  5621.9    0.07       0
Bank Sta=5190.8,5195.1
Exp/Cntr=0.3,0.1

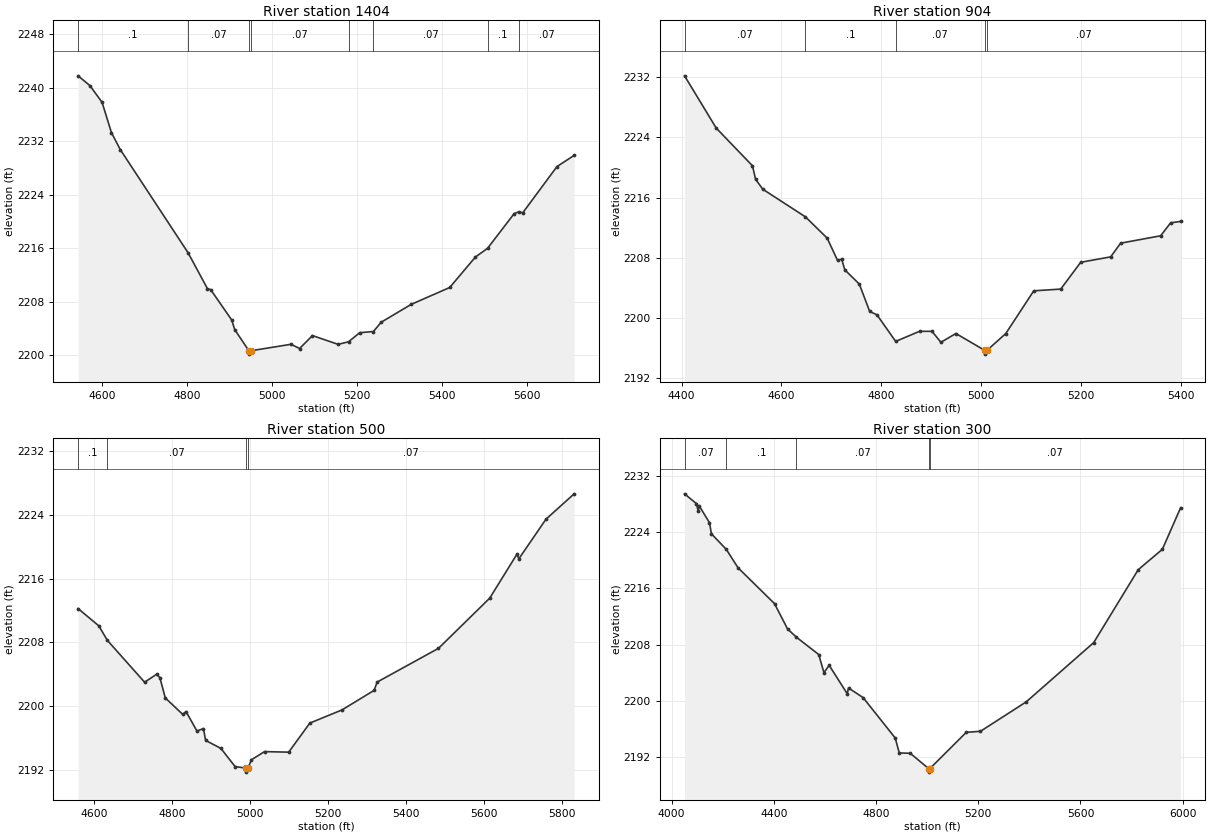
Type RM Length L Ch R = 1,1404,500,500,500
BEGIN DESCRIPTION:
Stream0089 3.0
END DESCRIPTION:
XS GIS Cut Line= 3
      1763775.01     13913225.01      1764125.00     13913525.00
      1764825.03     13913625.00
#Sta/Elev= 30
  4543.9 2241.76  4571.9 2240.29  4600.4 2237.79  4622.4 2233.27  4643.2 2230.74
  4802.6 2215.34  4848.5 2209.95  4856.1 2209.80  4905.5 2205.28  4912.7 2203.83
  4946.1 2200.66  4946.4 2200.16  4950.5 2200.66  5045.3 2201.63  5065.5 2201.00
  5095.8 2202.93  5156.4 2201.62  5180.9 2202.01  5206.9 2203.36  5239.4 2203.54
  5257.4 2204.92  5328.1 2207.59  5419.0 2210.12  5479.6 2214.68  5508.0 2215.97
  5570.6 2221.15  5581.6 2221.44  5590.8 2221.27  5671.6 2228.20  5712.0 2229.87
#Mann=8,-1,0
  4543.9     0.1       0  4802.6    0.07       0  4946.1    0.05       0
  4950.5    0.07       0  5180.9     0.1       0  5239.4    0.07       0
  5508.0     0.1       0  5581.6    0.07       0
Bank Sta=4946.1,4950.5
Exp/Cntr=0.3,0.1

Type RM Length L Ch R = 1,904,404,404,404
BEGIN DESCRIPTION:
Stream0089 2.0
END DESCRIPTION:
XS GIS Cut Line= 3
      1763675.02     13913525.03      1763974.40     13913916.46
      1764475.04     13913925.00
#Sta/Elev= 30
  4406.1 2232.18  4469.5 2225.24  4542.1 2220.23  4548.4 2218.43  4562.9 2217.11
  4648.3 2213.44  4691.7 2210.62  4712.5 2207.66  4720.8 2207.82  4727.1 2206.40
  4756.1 2204.52  4776.9 2200.88  4791.5 2200.43  4828.9 2196.90  4876.7 2198.24
  4901.7 2198.24  4919.5 2196.78  4949.5 2197.95  5007.3 2195.71  5007.6 2195.21
  5011.8 2195.71  5049.5 2197.95  5105.5 2203.62  5159.5 2203.85  5199.5 2207.41
  5259.5 2208.13  5279.5 2209.95  5359.6 2210.93  5379.6 2212.65  5399.6 2212.84
#Mann=5,-1,0
  4406.1    0.07       0  4648.3     0.1       0  4828.9    0.07       0
  5007.3    0.05       0  5011.8    0.07       0
Bank Sta=5007.3,5011.8
Exp/Cntr=0.3,0.1

Type RM Length L Ch R = 1,500,200,200,200
BEGIN DESCRIPTION:
Stream0089 1.0
END DESCRIPTION:
XS GIS Cut Line= 3
      1763725.00     13913875.00      1763925.00     13914275.00
      1764724.96     13914474.99
#Sta/Elev= 30
  4559.2 2212.24  4612.3 2210.08  4634.1 2208.27  4729.7 2203.02  4760.4 2204.01
  4768.8 2203.60  4782.8 2201.05  4827.5 2198.99  4835.9 2199.35  4863.9 2196.91
  4880.6 2197.21  4886.2 2195.73  4925.4 2194.73  4961.7 2192.46  4990.1 2192.26
  4990.5 2191.76  4994.7 2192.26  5003.6 2193.31  5037.3 2194.33  5099.2 2194.26
  5153.3 2197.90  5235.8 2199.55  5318.2 2202.00  5326.0 2203.04  5483.2 2207.26
  5614.6 2213.55  5684.2 2219.04  5689.3 2218.48  5758.9 2223.44  5831.0 2226.61
#Mann=4,-1,0
  4559.2     0.1       0  4634.1    0.07       0  4990.1    0.05       0
  4994.7    0.07       0
Bank Sta=4990.1,4994.7
Exp/Cntr=0.3,0.1

Type RM Length L Ch R = 1,300,0,0,0
BEGIN DESCRIPTION:
Stream0089 0.0
END DESCRIPTION:
XS GIS Cut Line= 4
      1763609.83     13913539.23      1763748.95     13914268.23
      1763946.52     13914607.39      1764747.91     13914698.40
#Sta/Elev= 30
  4050.6 2229.44  4097.2 2228.04  4103.6 2227.03  4108.7 2227.68  4148.1 2225.34
  4155.7 2223.75  4213.9 2221.54  4259.9 2218.92  4402.6 2213.82  4453.5 2210.23
  4487.7 2209.06  4575.7 2206.58  4596.0 2204.00  4616.4 2205.05  4687.1 2201.01
  4692.2 2201.82  4749.4 2200.45  4875.1 2194.70  4890.8 2192.58  4933.8 2192.53
  5005.9 2190.35  5006.3 2189.85  5010.5 2190.35  5153.0 2195.51  5208.6 2195.66
  5387.8 2199.85  5651.6 2208.27  5825.8 2218.64  5920.4 2221.55  5991.8 2227.46
#Mann=5,-1,0
  4050.6    0.07       0  4213.9     0.1       0  4487.7    0.07       0
  5005.9    0.05       0  5010.5    0.07       0
Bank Sta=5005.9,5010.5
Exp/Cntr=0.3,0.1

Chan Stop Cuts=-1