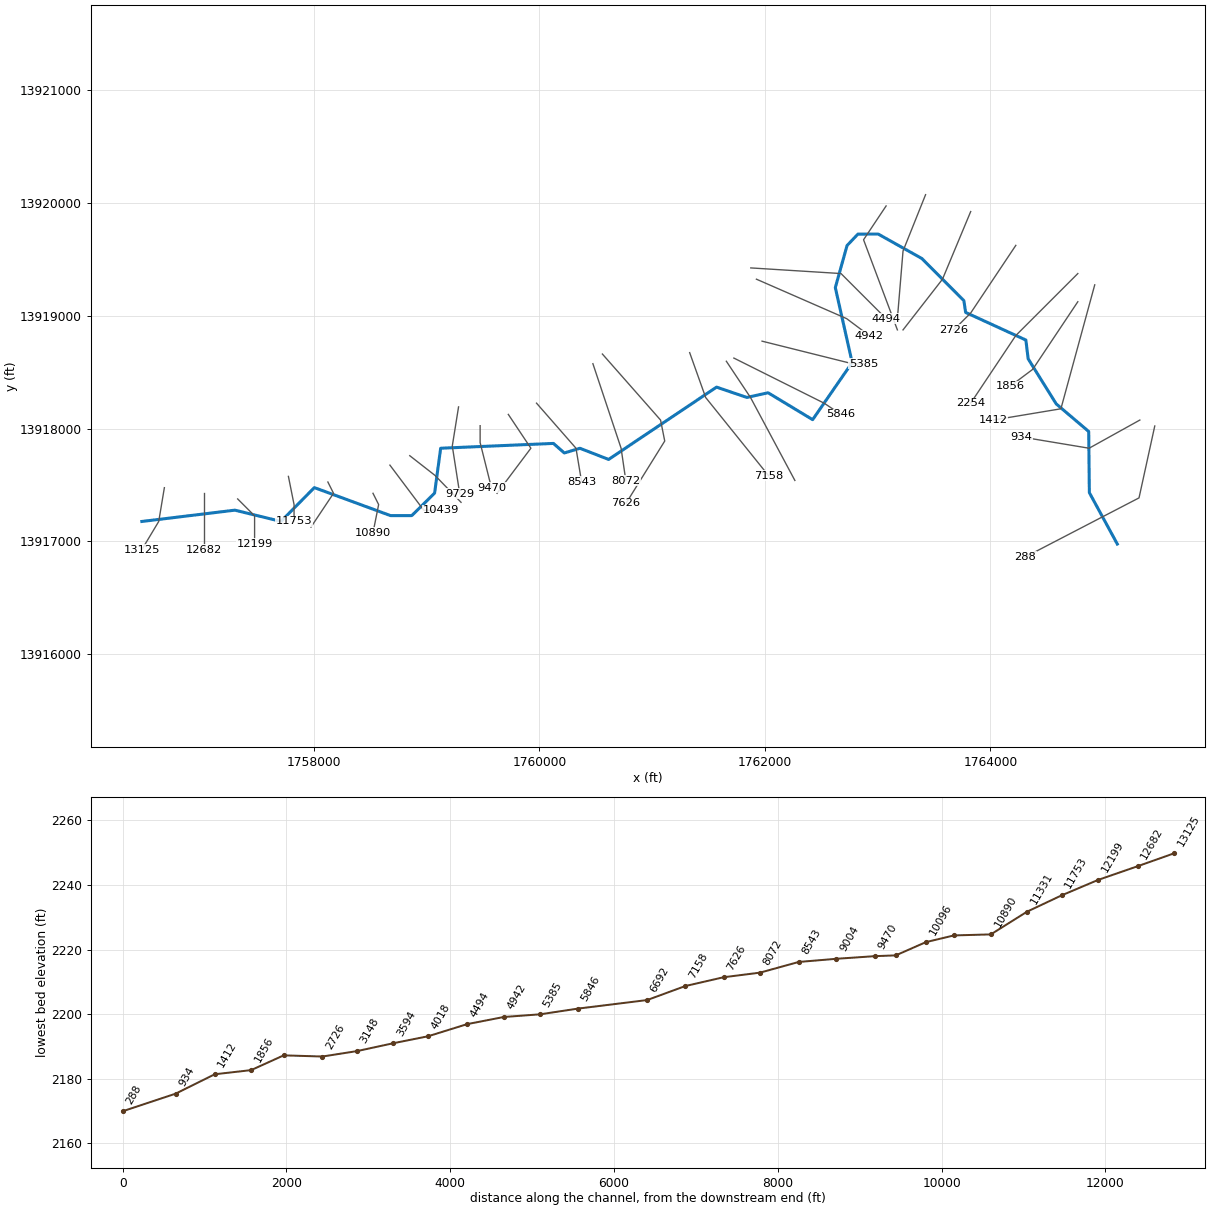
--- Stream0090.prj (project) ---

Proj Title=Stream0090 Base Level Engineering
Current Plan=p01
Default Exp/Contr=0.3,0.1
English Units
Geom File=g01
Flow File=f01
Plan File=p01
BEGIN DESCRIPTION:
Stream0090
END DESCRIPTION:

--- Stream0090.p01 (plan) ---

Plan Title=Multiple Run
Short Identifier=Multiple
Geom File=g01
Flow File=f01
Subcritical Flow
K Sum by GR= 0
Std Step Tol= 0.01
Critical Tol= 0.01
Num of Std Step Trials= 20
Max Error Tol= 0.3
Flow Tol Ratio= 0.001
Split Flow NTrial= 30
Split Flow Tol= 0.02
Split Flow Ratio= 0.02
Log Output Level= 0
Friction Slope Method= 1
Unsteady Friction Slope Method= 2
Unsteady Bridges Friction Slope Method= 1
Parabolic Critical Depth
Global Vel Dist=  1 , 1 , 1
Global Log Level= 0
CheckData=True
Encroach Param= -1, 0, 0, 0
BEGIN DESCRIPTION:
Multiple Run
END DESCRIPTION:

--- Stream0090.f01 (steady flow) ---

Flow Title=Multiple
Number of Profiles=7
Profile Names=10-year,25-year,50-year,1pct_min,100-year,1pct_plu,500-year
River Rch & RM= Stream0090,Reach-1,13125
    1636    2854    4034    2748    5484   10941   10031
River Rch & RM= Stream0090,Reach-1,9729
    2409    4266    6087    4180    8341   16642   15508
River Rch & RM= Stream0090,Reach-1,4018
    3192    5722    8233    5695   11363   22672   21438
Boundary for River Rch & Prof#=Stream0090,Reach-1,1
Up Type=0
Dn Type=3
Dn Slope=0.005
Boundary for River Rch & Prof#=Stream0090,Reach-1,2
Up Type=0
Dn Type=3
Dn Slope=0.005
Boundary for River Rch & Prof#=Stream0090,Reach-1,3
Up Type=0
Dn Type=3
Dn Slope=0.005
Boundary for River Rch & Prof#=Stream0090,Reach-1,4
Up Type=0
Dn Type=3
Dn Slope=0.005
Boundary for River Rch & Prof#=Stream0090,Reach-1,5
Up Type=0
Dn Type=3
Dn Slope=0.005
Boundary for River Rch & Prof#=Stream0090,Reach-1,6
Up Type=0
Dn Type=3
Dn Slope=0.005
Boundary for River Rch & Prof#=Stream0090,Reach-1,7
Up Type=0
Dn Type=3
Dn Slope=0.005

--- Stream0090.g01 (geometry) ---

Geom Title=Existing Conditions

River Reach=Stream0090,Reach-1
Reach XY= 30
      1756475.00     13917175.00      1757300.00     13917275.40
      1757709.16     13917175.66      1758004.83     13917475.46
      1758680.86     13917227.06      1758869.07     13917227.24
      1759071.25     13917426.55      1759125.00     13917825.00
      1760125.10     13917867.66      1760221.58     13917782.83
      1760359.72     13917824.61      1760614.38     13917725.60
      1761571.58     13918367.21      1761840.22     13918275.51
      1762028.42     13918317.21      1762423.51     13918078.45
      1762773.92     13918585.54      1762624.60     13919250.00
      1762728.49     13919623.55      1762825.00     13919725.00
      1763004.87     13919725.40      1763391.75     13919508.54
      1763764.46     13919134.74      1763780.11     13919030.11
      1764314.38     13918785.00      1764334.58     13918618.45
      1764583.04     13918218.67      1764871.46     13917973.54
      1764877.24     13917430.93      1765125.00     13916975.00

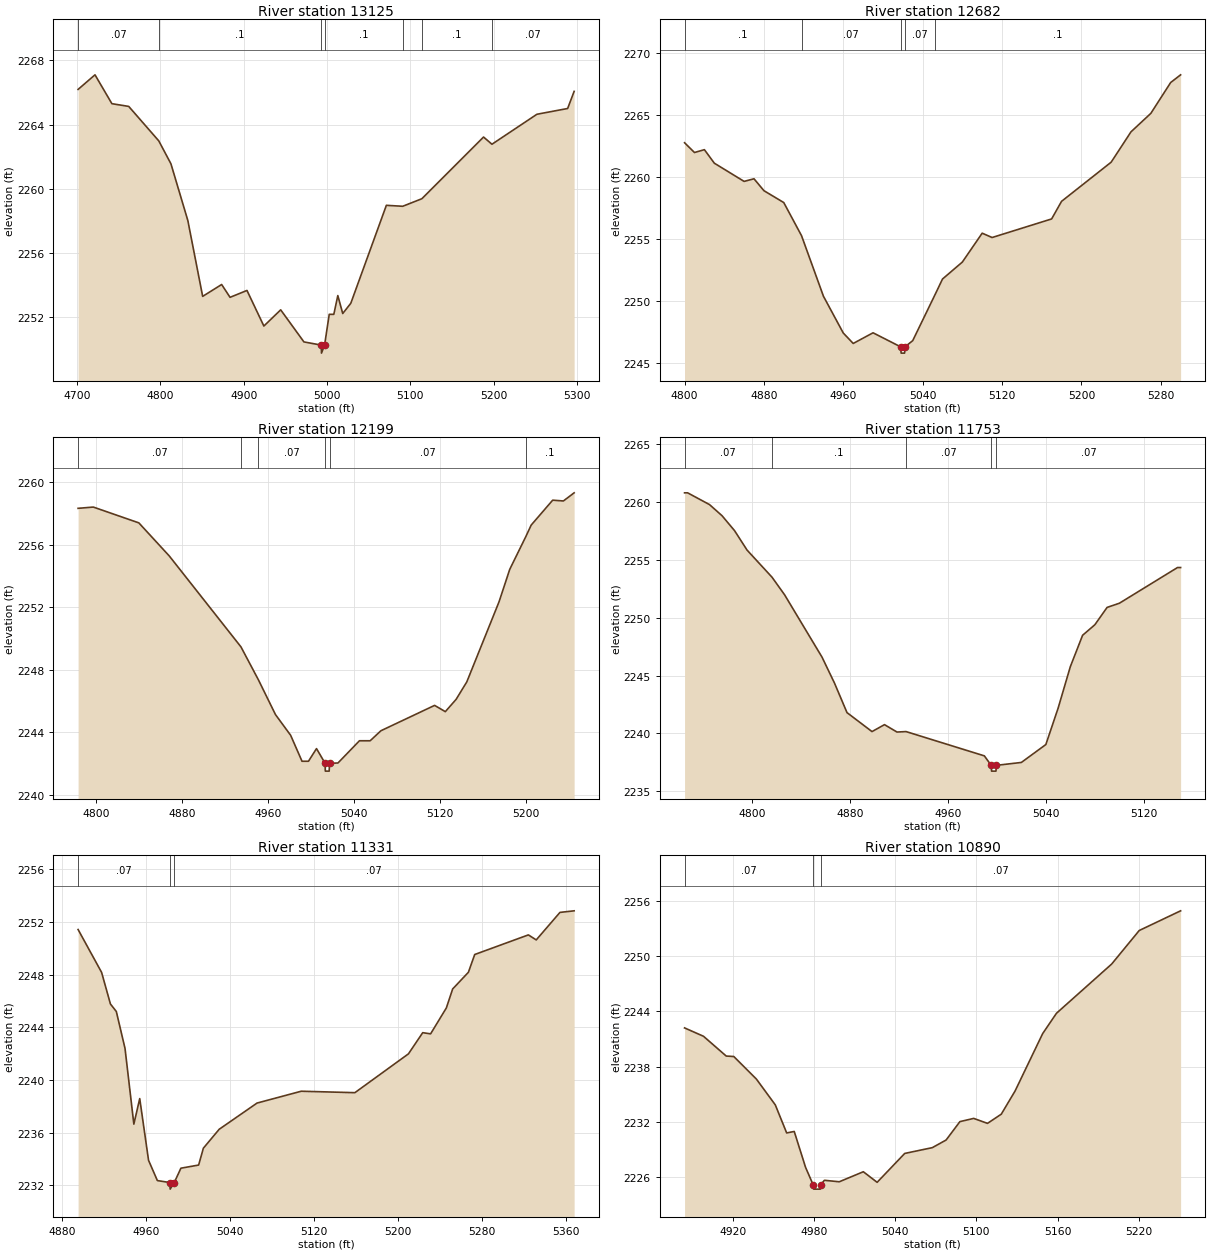
Type RM Length L Ch R = 1,13125,443,443,443
BEGIN DESCRIPTION:
Stream0090 27.0
END DESCRIPTION:
XS GIS Cut Line= 3
      1756675.00     13917475.02      1756625.00     13917175.00
      1756475.00     13916925.00
#Sta/Elev= 30
  4701.1 2266.19  4721.4 2267.10  4741.7 2265.30  4761.9 2265.13  4798.0 2262.98
  4812.6 2261.55  4832.9 2258.01  4850.7 2253.28  4873.5 2254.02  4883.6 2253.22
  4903.9 2253.65  4924.2 2251.43  4944.4 2252.44  4972.3 2250.44  4993.1 2250.24
  4993.4 2249.74  4997.1 2250.24  5002.7 2252.16  5008.2 2252.16  5013.0 2253.33
  5018.9 2252.21  5028.6 2252.85  5071.3 2258.96  5090.9 2258.90  5113.9 2259.37
  5188.0 2263.22  5198.1 2262.77  5252.1 2264.64  5289.0 2265.00  5296.8 2266.07
#Mann=7,-1,0
  4701.1    0.07       0  4798.0     0.1       0  4993.1    0.05       0
  4997.1     0.1       0  5090.9    0.07       0  5113.9     0.1       0
  5198.1    0.07       0
Bank Sta=4993.1,4997.1
Exp/Cntr=0.3,0.1

Type RM Length L Ch R = 1,12682,483,483,483
BEGIN DESCRIPTION:
Stream0090 26.0
END DESCRIPTION:
XS GIS Cut Line= 3
      1757025.00     13917425.00      1757025.00     13917225.00
      1757025.00     13916925.00
#Sta/Elev= 30
  4800.0 2262.75  4810.0 2261.96  4820.0 2262.19  4830.0 2261.10  4860.0 2259.63
  4870.0 2259.84  4880.0 2258.88  4900.0 2257.92  4917.9 2255.25  4940.0 2250.36
  4960.0 2247.39  4970.0 2246.55  4990.0 2247.41  5018.0 2246.27  5018.3 2245.77
  5021.8 2245.77  5022.1 2246.27  5030.0 2246.78  5052.9 2250.56  5060.0 2251.75
  5080.0 2253.12  5100.0 2255.45  5110.0 2255.10  5170.0 2256.60  5180.0 2258.02
  5230.0 2261.18  5250.0 2263.63  5270.0 2265.12  5290.0 2267.61  5300.0 2268.23
#Mann=5,-1,0
  4800.0     0.1       0  4917.9    0.07       0  5018.0    0.05       0
  5022.1    0.07       0  5052.9     0.1       0
Bank Sta=5018,5022.1
Exp/Cntr=0.3,0.1

Type RM Length L Ch R = 1,12199,446,446,446
BEGIN DESCRIPTION:
Stream0090 25.0
END DESCRIPTION:
XS GIS Cut Line= 3
      1757324.99     13917375.01      1757475.00     13917225.00
      1757475.00     13916975.04
#Sta/Elev= 30
  4783.2 2258.32  4797.4 2258.40  4839.8 2257.39  4868.1 2255.28  4934.9 2249.47
  4951.2 2247.36  4967.1 2245.14  4981.2 2243.82  4991.8 2242.16  4997.8 2242.16
  5005.3 2242.97  5013.3 2242.03  5013.5 2241.53  5017.1 2241.53  5017.4 2242.03
  5025.3 2242.05  5045.3 2243.47  5055.3 2243.47  5065.3 2244.11  5115.3 2245.73
  5125.3 2245.33  5135.3 2246.11  5145.3 2247.23  5175.3 2252.34  5185.3 2254.42
  5200.4 2256.53  5205.3 2257.25  5225.3 2258.84  5235.3 2258.79  5245.3 2259.31
#Mann=6,-1,0
  4783.2    0.07       0  4934.9     0.1       0  4951.2    0.07       0
  5013.3    0.05       0  5017.4    0.07       0  5200.4     0.1       0
Bank Sta=5013.3,5017.4
Exp/Cntr=0.3,0.1

Type RM Length L Ch R = 1,11753,422,422,422
BEGIN DESCRIPTION:
Stream0090 24.0
END DESCRIPTION:
XS GIS Cut Line= 3
      1757775.00     13917574.99      1757825.00     13917325.00
      1757825.00     13917175.04
#Sta/Elev= 30
  4745.1 2260.81  4747.6 2260.81  4765.5 2259.79  4775.7 2258.83  4785.9 2257.54
  4796.1 2255.86  4816.5 2253.51  4826.7 2252.00  4857.3 2246.60  4867.5 2244.35
  4877.7 2241.80  4898.1 2240.16  4908.3 2240.76  4918.5 2240.12  4925.9 2240.16
  4989.8 2238.06  4995.4 2237.24  4995.7 2236.74  4999.3 2236.74  4999.6 2237.24
  5020.0 2237.49  5040.0 2239.04  5050.0 2242.18  5060.0 2245.78  5070.0 2248.49
  5080.0 2249.40  5090.0 2250.90  5100.0 2251.26  5147.5 2254.35  5150.0 2254.35
#Mann=5,-1,0
  4745.1    0.07       0  4816.5     0.1       0  4925.9    0.07       0
  4995.4    0.05       0  4999.6    0.07       0
Bank Sta=4995.4,4999.6
Exp/Cntr=0.3,0.1

Type RM Length L Ch R = 1,11331,441,441,441
BEGIN DESCRIPTION:
Stream0090 23.0
END DESCRIPTION:
XS GIS Cut Line= 3
      1758124.99     13917525.02      1758175.00     13917425.00
      1757974.99     13917124.98
#Sta/Elev= 30
  4895.3 2251.43  4917.7 2248.17  4926.1 2245.77  4931.7 2245.20  4940.0 2242.39
  4948.4 2236.64  4954.0 2238.58  4962.4 2233.89  4970.8 2232.35  4982.7 2232.20
  4983.0 2231.70  4986.9 2232.20  4993.2 2233.29  5010.1 2233.53  5014.6 2234.81
  5029.7 2236.25  5065.7 2238.24  5107.8 2239.14  5158.9 2239.03  5209.9 2241.98
  5223.5 2243.59  5231.0 2243.50  5246.0 2245.47  5252.0 2246.91  5267.0 2248.18
  5273.0 2249.53  5324.1 2251.02  5331.6 2250.64  5354.2 2252.73  5367.7 2252.85
#Mann=3,-1,0
  4895.3    0.07       0  4982.7    0.05       0  4986.9    0.07       0
Bank Sta=4982.7,4986.9
Exp/Cntr=0.3,0.1

Type RM Length L Ch R = 1,10890,451,451,451
BEGIN DESCRIPTION:
Stream0090 22.0
END DESCRIPTION:
XS GIS Cut Line= 3
      1758524.99     13917425.03      1758575.00     13917325.00
      1758525.00     13917074.99
#Sta/Elev= 30
  4884.2 2242.21  4898.2 2241.30  4915.0 2239.15  4920.6 2239.10  4937.3 2236.65
  4951.3 2233.84  4959.7 2230.79  4965.3 2230.95  4973.7 2227.04  4979.2 2225.18
  4979.7 2224.68  4984.5 2224.68  4984.9 2225.18  4987.6 2225.64  4998.6 2225.48
  5016.4 2226.57  5026.6 2225.42  5047.0 2228.56  5067.4 2229.19  5077.6 2230.02
  5087.8 2232.02  5098.0 2232.37  5108.2 2231.83  5118.4 2232.83  5128.6 2235.35
  5149.0 2241.59  5159.2 2243.80  5200.0 2249.15  5220.4 2252.80  5251.0 2254.94
#Mann=3,-1,0
  4884.2    0.07       0  4979.2    0.05       0  4984.9    0.07       0
Bank Sta=4979.2,4984.9
Exp/Cntr=0.3,0.1

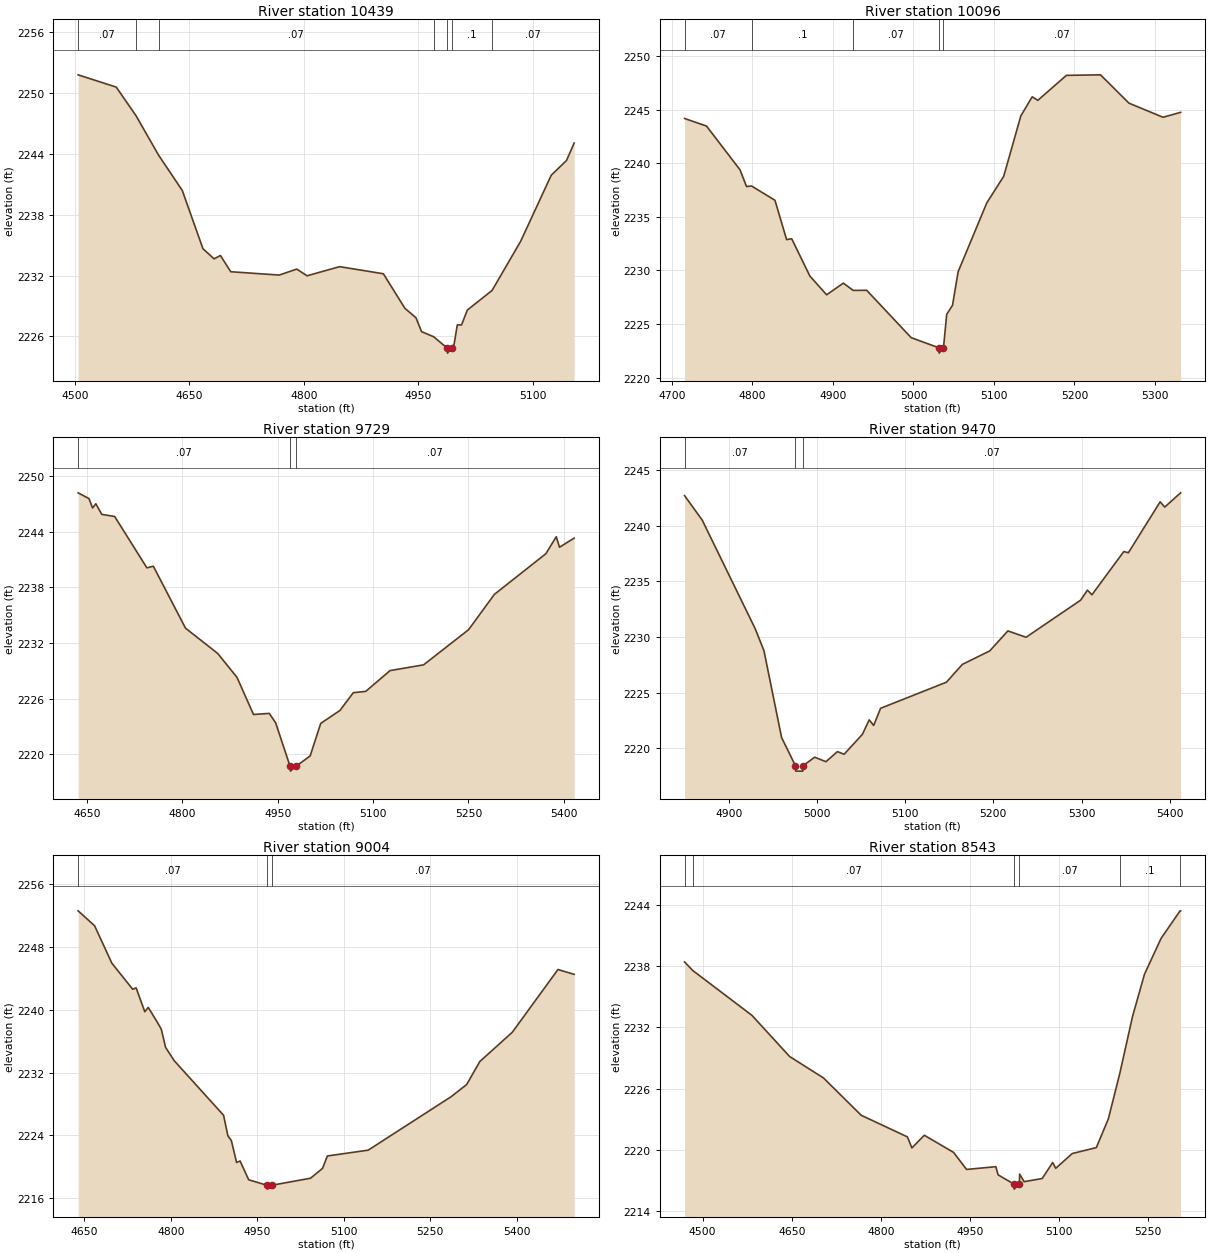
Type RM Length L Ch R = 1,10439,343,343,343
BEGIN DESCRIPTION:
Stream0090 21.0
END DESCRIPTION:
XS GIS Cut Line= 3
      1758674.98     13917675.03      1758975.00     13917275.00
      1759124.96     13917275.00
#Sta/Elev= 30
  4504.3 2251.78  4554.3 2250.57  4580.4 2247.73  4609.9 2243.85  4640.8 2240.39
  4667.9 2234.65  4682.5 2233.65  4690.8 2233.98  4704.3 2232.38  4767.9 2232.05
  4790.8 2232.64  4804.3 2231.98  4847.0 2232.88  4904.3 2232.18  4932.5 2228.78
  4947.0 2227.85  4954.3 2226.48  4970.3 2225.97  4987.9 2224.86  4988.4 2224.36
  4993.7 2224.86  4997.0 2225.23  5001.2 2227.14  5006.8 2227.14  5014.3 2228.60
  5046.8 2230.54  5084.3 2235.39  5124.3 2241.89  5144.3 2243.34  5154.3 2245.06
#Mann=7,-1,0
  4504.3    0.07       0  4580.4     0.1       0  4609.9    0.07       0
  4970.3     0.1       0  4987.9    0.05       0  4993.7     0.1       0
  5046.8    0.07       0
Bank Sta=4987.9,4993.7
Exp/Cntr=0.3,0.1

Type RM Length L Ch R = 1,10096,367,367,367
BEGIN DESCRIPTION:
Stream0090 20.0
END DESCRIPTION:
XS GIS Cut Line= 3
      1758850.99     13917758.76      1759075.61     13917583.11
      1759305.80     13917345.05
#Sta/Elev= 30
  4715.6 2244.17  4742.9 2243.46  4784.5 2239.38  4792.6 2237.82  4798.8 2237.87
  4827.9 2236.54  4842.4 2232.87  4848.7 2232.95  4871.3 2229.47  4892.1 2227.72
  4912.9 2228.81  4925.1 2228.13  4941.9 2228.14  4997.2 2223.72  5031.5 2222.78
  5031.9 2222.28  5037.3 2222.78  5041.3 2225.90  5048.5 2226.74  5055.5 2229.87
  5091.0 2236.28  5112.1 2238.77  5133.4 2244.41  5147.5 2246.19  5154.5 2245.86
  5190.0 2248.19  5232.4 2248.24  5267.7 2245.60  5310.1 2244.28  5331.9 2244.74
#Mann=5,-1,0
  4715.6    0.07       0  4798.8     0.1       0  4925.1    0.07       0
  5031.5    0.05       0  5037.3    0.07       0
Bank Sta=5031.5,5037.3
Exp/Cntr=0.3,0.1

Type RM Length L Ch R = 1,9729,259,259,259
BEGIN DESCRIPTION:
Stream0090 T
END DESCRIPTION:
XS GIS Cut Line= 3
      1759283.71     13918191.88      1759228.15     13917844.61
      1759294.12     13917421.00
#Sta/Elev= 30
  4636.0 2248.17  4653.1 2247.55  4658.8 2246.54  4663.9 2246.99  4673.3 2245.85
  4693.6 2245.62  4744.2 2240.09  4754.4 2240.26  4805.0 2233.59  4855.6 2230.87
  4886.0 2228.29  4912.0 2224.29  4936.7 2224.41  4946.8 2223.40  4969.6 2218.69
  4970.1 2218.19  4978.5 2218.69  5001.1 2219.83  5017.7 2223.33  5048.0 2224.73
  5069.0 2226.64  5088.5 2226.78  5126.8 2229.02  5179.6 2229.64  5250.4 2233.43
  5290.9 2237.23  5371.9 2241.61  5388.3 2243.44  5393.4 2242.31  5416.4 2243.29
#Mann=3,-1,0
  4636.0    0.07       0  4969.6    0.05       0  4978.5    0.07       0
Bank Sta=4969.6,4978.5
Exp/Cntr=0.3,0.1

Type RM Length L Ch R = 1,9470,466,466,466
BEGIN DESCRIPTION:
Stream0090 19.0
END DESCRIPTION:
XS GIS Cut Line= 3
      1759475.00     13918025.02      1759475.00     13917875.00
      1759574.99     13917475.03
#Sta/Elev= 30
  4850.0 2242.72  4870.0 2240.52  4930.0 2230.76  4940.0 2228.77  4960.0 2220.96
  4975.6 2218.44  4976.1 2217.94  4984.0 2217.94  4984.5 2218.44  4997.5 2219.19
  5010.3 2218.79  5023.2 2219.69  5030.9 2219.46  5051.6 2221.25  5059.3 2222.55
  5064.4 2222.05  5072.2 2223.59  5146.9 2225.94  5164.9 2227.54  5195.9 2228.75
  5216.5 2230.55  5237.1 2229.98  5298.9 2233.31  5306.7 2234.22  5311.8 2233.80
  5347.9 2237.69  5353.1 2237.58  5389.1 2242.16  5394.3 2241.69  5412.3 2242.97
#Mann=3,-1,0
  4850.0    0.07       0  4975.6    0.05       0  4984.5    0.07       0
Bank Sta=4975.6,4984.5
Exp/Cntr=0.3,0.1

Type RM Length L Ch R = 1,9004,461,461,461
BEGIN DESCRIPTION:
Stream0090 18.0
END DESCRIPTION:
XS GIS Cut Line= 3
      1759724.98     13918125.03      1759925.00     13917825.00
      1759624.99     13917424.99
#Sta/Elev= 30
  4638.9 2252.63  4667.5 2250.73  4697.5 2245.95  4733.6 2242.63  4739.6 2242.80
  4754.6 2239.76  4760.6 2240.31  4775.6 2238.51  4783.2 2237.54  4790.7 2235.21
  4805.7 2233.51  4891.3 2226.55  4898.8 2223.93  4904.8 2223.32  4913.9 2220.53
  4919.9 2220.72  4934.9 2218.32  4966.5 2217.63  4967.0 2217.13  4975.4 2217.63
  5042.2 2218.52  5063.0 2219.78  5071.4 2221.36  5142.2 2222.10  5285.9 2228.91
  5313.0 2230.47  5335.9 2233.41  5392.2 2237.14  5471.4 2245.14  5499.5 2244.53
#Mann=3,-1,0
  4638.9    0.07       0  4966.5    0.05       0  4975.4    0.07       0
Bank Sta=4966.5,4975.4
Exp/Cntr=0.3,0.1

Type RM Length L Ch R = 1,8543,471,471,471
BEGIN DESCRIPTION:
Stream0090 17.0
END DESCRIPTION:
XS GIS Cut Line= 3
      1759974.98     13918225.02      1760325.00     13917825.00
      1760375.00     13917524.97
#Sta/Elev= 30
  4469.5 2238.42  4483.3 2237.58  4582.9 2233.19  4646.5 2229.15  4703.5 2227.05
  4767.1 2223.39  4844.9 2221.27  4852.5 2220.19  4873.4 2221.43  4922.7 2219.75
  4944.6 2218.08  4993.9 2218.35  4997.7 2217.55  5024.3 2216.65  5024.8 2216.15
  5033.5 2216.65  5034.0 2217.62  5041.6 2216.88  5072.0 2217.19  5089.7 2218.76
  5094.8 2218.19  5122.7 2219.64  5163.2 2220.22  5183.5 2223.04  5202.9 2227.53
  5224.1 2233.05  5244.3 2237.21  5272.2 2240.72  5304.3 2243.43  5305.2 2243.43
#Mann=6,-1,0
  4469.5     0.1       0  4483.3    0.07       0  5024.3    0.05       0
  5033.5    0.07       0  5202.9     0.1       0  5304.3    0.07       0
Bank Sta=5024.3,5033.5
Exp/Cntr=0.3,0.1

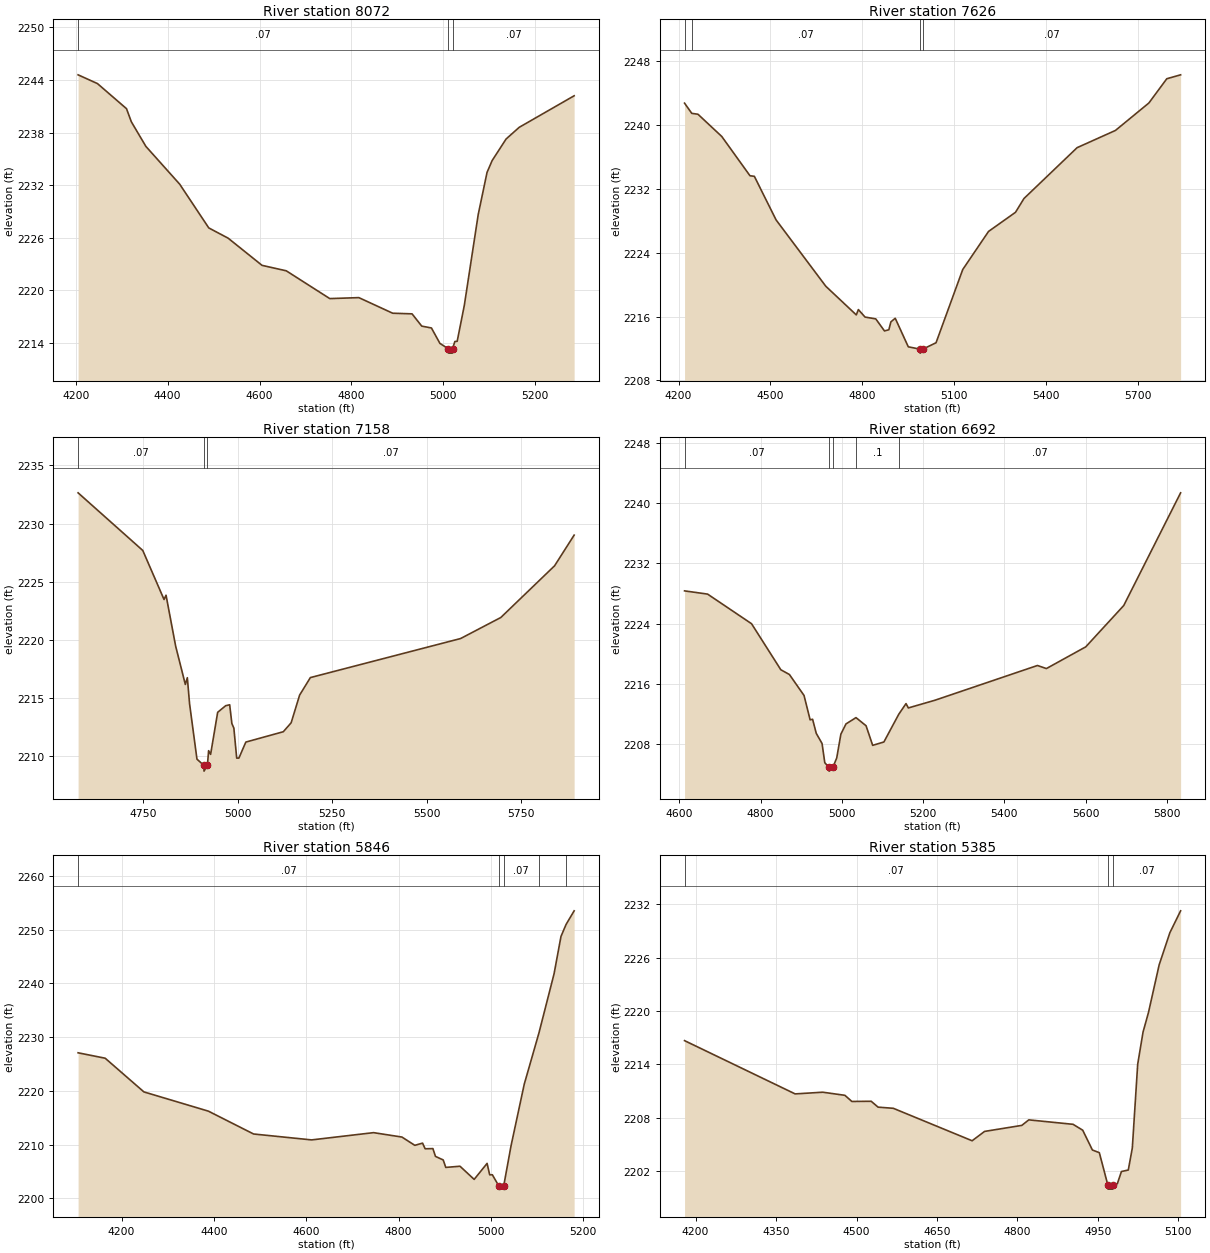
Type RM Length L Ch R = 1,8072,446,446,446
BEGIN DESCRIPTION:
Stream0090 16.0
END DESCRIPTION:
XS GIS Cut Line= 3
      1760474.99     13918575.02      1760725.00     13917825.00
      1760766.81     13917538.32
#Sta/Elev= 30
  4204.9 2244.59  4247.1 2243.59  4310.3 2240.73  4320.9 2239.23  4352.5 2236.43
  4426.3 2232.11  4489.5 2227.13  4531.7 2225.96  4605.5 2222.86  4658.2 2222.24
  4753.0 2219.07  4816.3 2219.18  4890.1 2217.40  4932.2 2217.33  4953.3 2215.93
  4974.4 2215.72  4992.9 2213.96  5011.0 2213.35  5011.5 2212.85  5019.8 2212.85
  5020.3 2213.35  5025.4 2214.17  5030.5 2214.20  5046.0 2218.29  5076.3 2228.66
  5095.5 2233.46  5106.6 2234.81  5137.0 2237.27  5165.5 2238.60  5285.2 2242.20
#Mann=3,-1,0
  4204.9    0.07       0  5011.0    0.05       0  5020.3    0.07       0
Bank Sta=5011,5020.3
Exp/Cntr=0.3,0.1

Type RM Length L Ch R = 1,7626,468,468,468
BEGIN DESCRIPTION:
Stream0090 15.0
END DESCRIPTION:
XS GIS Cut Line= 4
      1760559.16     13918660.78      1761075.00     13918075.00
      1761111.92     13917888.72      1760769.07     13917337.00
#Sta/Elev= 30
  4219.7 2242.75  4243.3 2241.47  4263.5 2241.36  4341.3 2238.57  4433.4 2233.65
  4447.6 2233.58  4518.7 2228.11  4681.0 2219.80  4780.6 2216.21  4787.3 2216.88
  4809.1 2215.94  4844.2 2215.71  4872.6 2214.20  4886.9 2214.35  4893.6 2215.34
  4907.7 2215.79  4950.4 2212.21  4988.5 2211.92  4989.0 2211.42  4997.8 2211.92
  5041.0 2212.72  5128.2 2221.90  5212.4 2226.67  5300.5 2229.07  5328.2 2230.80
  5501.7 2237.17  5626.9 2239.33  5736.1 2242.77  5794.6 2245.81  5839.7 2246.30
#Mann=4,-1,0
  4219.7     0.1       0  4243.3    0.07       0  4988.5    0.05       0
  4997.8    0.07       0
Bank Sta=4988.5,4997.8
Exp/Cntr=0.3,0.1

Type RM Length L Ch R = 1,7158,466,466,466
BEGIN DESCRIPTION:
Stream0090 14.0
END DESCRIPTION:
XS GIS Cut Line= 3
      1761333.10     13918673.10      1761475.00     13918275.00
      1762033.37     13917580.71
#Sta/Elev= 30
  4577.1 2232.64  4748.4 2227.68  4804.7 2223.46  4810.0 2223.83  4835.5 2219.44
  4861.1 2216.15  4866.4 2216.73  4872.3 2214.49  4891.9 2209.72  4910.1 2209.19
  4910.6 2208.69  4919.6 2209.19  4922.7 2210.45  4928.0 2210.13  4946.7 2213.75
  4967.9 2214.32  4978.5 2214.40  4984.3 2212.79  4989.6 2212.39  4997.1 2209.81
  5002.9 2209.81  5021.3 2211.19  5120.5 2212.08  5141.3 2212.85  5163.7 2215.23
  5192.2 2216.74  5590.0 2220.10  5696.5 2221.91  5838.9 2226.36  5890.7 2229.00
#Mann=3,-1,0
  4577.1    0.07       0  4910.1    0.05       0  4919.6    0.07       0
Bank Sta=4910.1,4919.6
Exp/Cntr=0.3,0.1

Type RM Length L Ch R = 1,6692,846,846,846
BEGIN DESCRIPTION:
Stream0090 13.0
END DESCRIPTION:
XS GIS Cut Line= 3
      1761658.28     13918596.76      1761873.11     13918274.13
      1762265.97     13917539.04
#Sta/Elev= 30
  4612.9 2228.35  4669.6 2227.92  4777.8 2223.98  4849.9 2217.85  4871.0 2217.22
  4907.0 2214.43  4922.0 2211.19  4928.1 2211.26  4937.1 2209.39  4951.4 2208.03
  4958.1 2205.48  4968.3 2204.86  4968.8 2204.36  4978.0 2204.86  4987.5 2206.12
  4997.7 2209.28  5010.2 2210.64  5034.9 2211.48  5059.7 2210.40  5076.0 2207.79
  5103.6 2208.24  5140.1 2211.92  5158.1 2213.35  5163.8 2212.77  5229.6 2213.80
  5481.6 2218.42  5503.6 2218.01  5600.5 2220.90  5694.0 2226.40  5834.0 2241.40
#Mann=5,-1,0
  4612.9    0.07       0  4968.3    0.05       0  4978.0    0.07       0
  5034.9     0.1       0  5140.1    0.07       0
Bank Sta=4968.3,4978
Exp/Cntr=0.3,0.1

Type RM Length L Ch R = 1,5846,461,461,461
BEGIN DESCRIPTION:
Stream0090 12.0
END DESCRIPTION:
XS GIS Cut Line= 3
      1761724.97     13918625.01      1762525.00     13918225.00
      1762674.97     13918125.02
#Sta/Elev= 30
  4105.7 2227.08  4164.4 2226.07  4248.3 2219.80  4388.0 2216.22  4485.9 2211.97
  4611.6 2210.87  4745.8 2212.22  4807.3 2211.40  4835.2 2209.86  4852.0 2210.27
  4857.6 2209.22  4874.4 2209.25  4880.0 2207.80  4896.7 2207.14  4902.3 2205.75
  4933.1 2205.97  4963.8 2203.52  4991.8 2206.50  4997.4 2204.38  5003.2 2204.38
  5017.8 2202.21  5018.3 2201.71  5027.6 2202.21  5043.7 2209.78  5072.3 2221.24
  5104.1 2230.76  5136.9 2241.78  5151.9 2248.74  5162.9 2250.96  5180.4 2253.50
#Mann=5,-1,0
  4105.7    0.07       0  5017.8    0.05       0  5027.6    0.07       0
  5104.1     0.1       0  5162.9    0.07       0
Bank Sta=5017.8,5027.6
Exp/Cntr=0.3,0.1

Type RM Length L Ch R = 1,5385,443,443,443
BEGIN DESCRIPTION:
Stream0090 11.0
END DESCRIPTION:
XS GIS Cut Line= 3
      1761975.03     13918774.99      1762775.00     13918575.00
      1762875.01     13918575.00
#Sta/Elev= 30
  4179.5 2216.65  4385.6 2210.66  4437.2 2210.85  4478.4 2210.50  4491.3 2209.81
  4527.4 2209.83  4540.2 2209.17  4568.6 2209.04  4715.5 2205.39  4738.7 2206.44
  4808.2 2207.12  4821.1 2207.74  4903.6 2207.24  4921.6 2206.58  4939.7 2204.35
  4952.6 2204.05  4968.3 2200.45  4968.8 2199.95  4977.6 2199.95  4978.1 2200.45
  4986.1 2200.55  4993.8 2201.93  5006.6 2202.10  5014.1 2204.58  5024.1 2213.99
  5034.1 2217.62  5044.1 2219.79  5064.1 2225.17  5084.1 2228.79  5104.1 2231.25
#Mann=3,-1,0
  4179.5    0.07       0  4968.3    0.05       0  4978.1    0.07       0
Bank Sta=4968.3,4978.1
Exp/Cntr=0.3,0.1

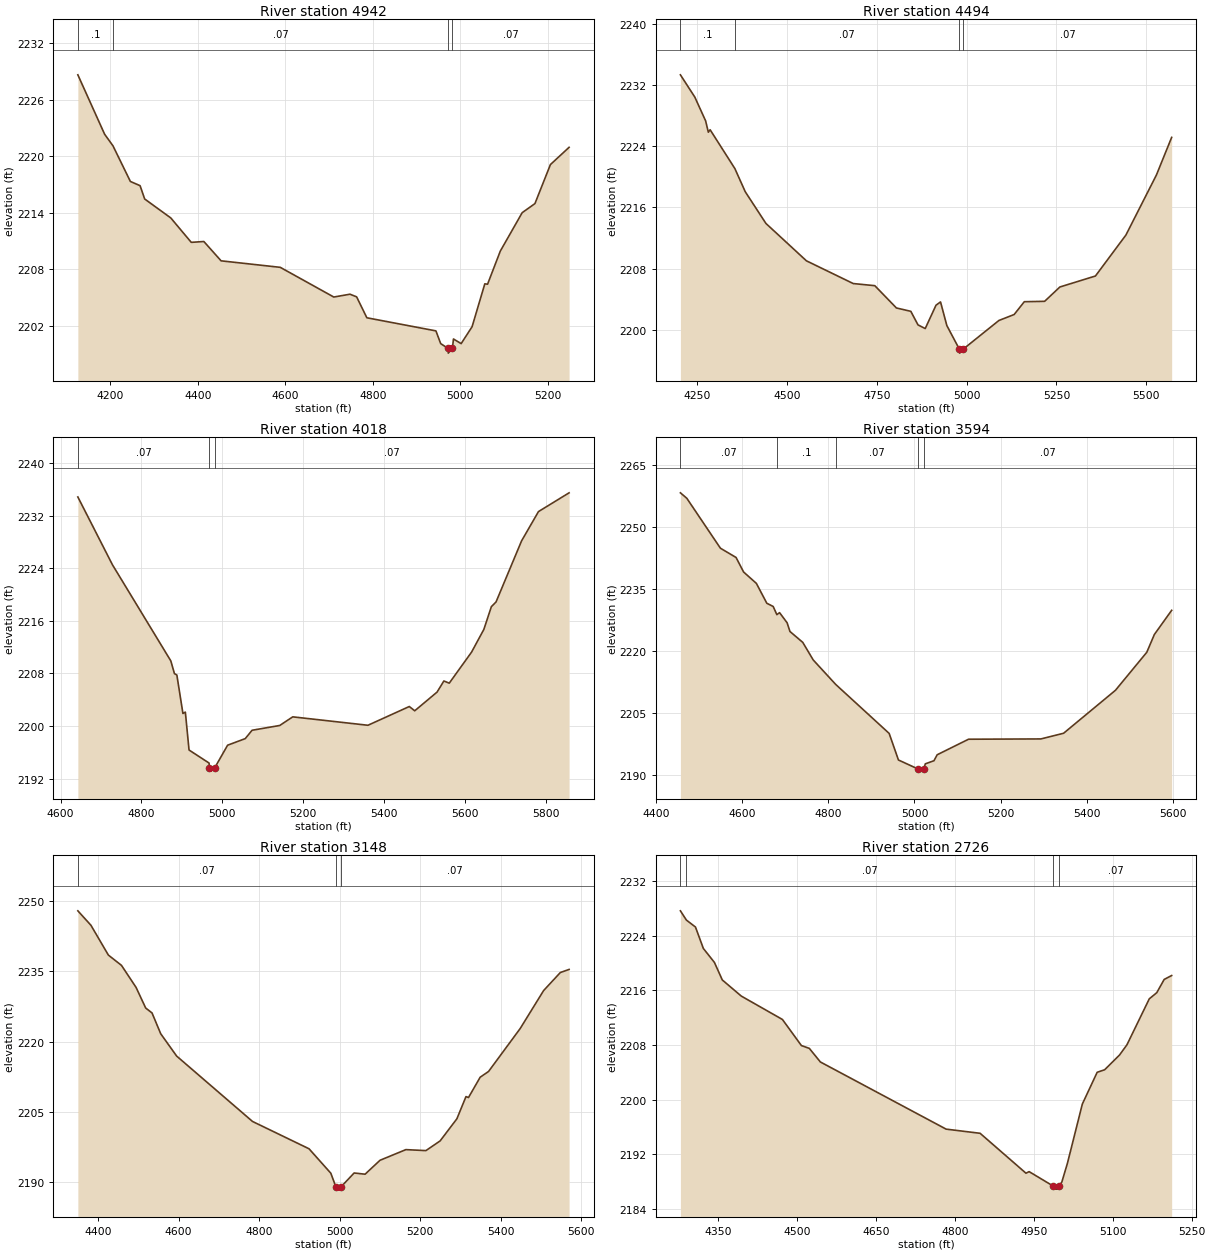
Type RM Length L Ch R = 1,4942,448,448,448
BEGIN DESCRIPTION:
Stream0090 10.0
END DESCRIPTION:
XS GIS Cut Line= 3
      1761924.97     13919325.01      1762725.00     13918975.00
      1762924.96     13918825.03
#Sta/Elev= 30
  4125.8 2228.64  4187.0 2222.34  4206.1 2221.11  4245.9 2217.33  4268.1 2216.88
  4278.6 2215.47  4338.3 2213.46  4385.1 2210.87  4413.9 2210.96  4453.3 2208.91
  4588.6 2208.22  4711.0 2205.07  4748.0 2205.37  4763.2 2205.09  4786.6 2202.87
  4944.5 2201.48  4955.4 2200.13  4972.3 2199.62  4972.8 2199.12  4982.2 2199.62
  4984.6 2200.62  5002.2 2200.13  5027.2 2201.92  5056.3 2206.47  5062.6 2206.43
  5091.8 2209.95  5141.8 2214.02  5170.9 2214.98  5206.3 2219.12  5249.0 2220.95
#Mann=4,-1,0
  4125.8     0.1       0  4206.1    0.07       0  4972.3    0.05       0
  4982.2    0.07       0
Bank Sta=4972.3,4982.2
Exp/Cntr=0.3,0.1

Type RM Length L Ch R = 1,4494,476,476,476
BEGIN DESCRIPTION:
Stream0090 9.0
END DESCRIPTION:
XS GIS Cut Line= 3
      1761874.96     13919425.00      1762675.00     13919375.00
      1763075.01     13918974.99
#Sta/Elev= 30
  4203.3 2233.39  4243.4 2230.47  4273.5 2227.35  4281.0 2225.87  4286.0 2226.19
  4354.9 2221.10  4383.7 2218.07  4441.3 2213.91  4554.0 2209.01  4684.3 2206.03
  4744.4 2205.75  4804.5 2202.83  4844.6 2202.39  4864.6 2200.61  4884.7 2200.13
  4914.7 2203.19  4927.3 2203.62  4944.8 2200.53  4979.9 2197.41  4980.4 2196.91
  4989.8 2197.41  5089.8 2201.19  5132.2 2201.97  5160.5 2203.65  5217.0 2203.70
  5259.5 2205.58  5358.5 2207.02  5443.3 2212.39  5528.2 2220.26  5570.6 2225.19
#Mann=4,-1,0
  4203.3     0.1       0  4354.9    0.07       0  4979.9    0.05       0
  4989.8    0.07       0
Bank Sta=4979.9,4989.8
Exp/Cntr=0.3,0.1

Type RM Length L Ch R = 1,4018,424,424,424
BEGIN DESCRIPTION:
Stream0090 8.0
END DESCRIPTION:
XS GIS Cut Line= 3
      1763075.02     13919975.03      1762875.00     13919675.00
      1763175.00     13918875.00
#Sta/Elev= 30
  4642.6 2234.83  4728.3 2224.51  4872.5 2209.92  4881.5 2207.98  4887.5 2207.77
  4902.5 2201.92  4908.5 2202.13  4917.6 2196.37  4967.1 2194.39  4968.2 2193.66
  4968.7 2193.16  4981.1 2193.66  5013.0 2197.10  5056.6 2198.10  5073.5 2199.37
  5142.0 2200.10  5174.1 2201.41  5360.1 2200.13  5462.4 2202.98  5475.8 2202.33
  5531.0 2205.17  5547.9 2206.86  5561.2 2206.53  5616.4 2211.25  5646.7 2214.69
  5665.4 2218.16  5676.9 2218.87  5740.1 2228.16  5781.9 2232.61  5857.6 2235.46
#Mann=3,-1,0
  4642.6    0.07       0  4968.2    0.05       0  4981.1    0.07       0
Bank Sta=4968.2,4981.1
Exp/Cntr=0.3,0.1

Type RM Length L Ch R = 1,3594,446,446,446
BEGIN DESCRIPTION:
Stream0090 7.0
END DESCRIPTION:
XS GIS Cut Line= 3
      1763425.00     13920074.99      1763225.00     13919575.00
      1763175.00     13918974.99
#Sta/Elev= 30
  4456.6 2258.18  4471.4 2256.87  4549.5 2244.81  4585.8 2242.58  4603.3 2239.07
  4633.0 2236.32  4657.2 2231.53  4672.0 2230.75  4680.5 2228.78  4686.8 2229.26
  4704.3 2226.82  4711.0 2224.71  4740.7 2222.08  4764.9 2217.85  4817.1 2211.94
  4941.3 2200.11  4962.8 2193.70  5008.7 2191.51  5009.2 2191.01  5021.6 2191.51
  5025.2 2192.77  5045.3 2193.52  5052.8 2194.96  5125.6 2198.71  5293.6 2198.78
  5346.3 2200.15  5466.7 2210.52  5539.5 2219.70  5557.0 2223.98  5597.2 2229.82
#Mann=5,-1,0
  4456.6    0.07       0  4680.5     0.1       0  4817.1    0.07       0
  5008.7    0.05       0  5021.6    0.07       0
Bank Sta=5008.7,5021.6
Exp/Cntr=0.3,0.1

Type RM Length L Ch R = 1,3148,422,422,422
BEGIN DESCRIPTION:
Stream0090 6.0
END DESCRIPTION:
XS GIS Cut Line= 3
      1763825.01     13919925.01      1763575.00     13919325.00
      1763225.00     13918875.00
#Sta/Elev= 30
  4350.0 2247.88  4382.5 2244.80  4425.8 2238.45  4458.3 2236.26  4494.6 2231.56
  4518.5 2227.16  4534.2 2226.12  4555.8 2221.68  4595.4 2216.92  4783.9 2202.98
  4924.2 2197.16  4978.3 2191.95  4990.8 2189.06  4991.3 2188.56  5003.8 2189.06
  5036.2 2192.00  5063.4 2191.74  5100.5 2194.71  5164.7 2196.98  5214.5 2196.77
  5249.8 2198.84  5291.4 2203.55  5314.0 2208.28  5320.3 2208.09  5349.3 2212.42
  5370.1 2213.64  5448.8 2222.81  5506.8 2230.88  5548.4 2234.73  5570.1 2235.39
#Mann=3,-1,0
  4350.0    0.07       0  4990.8    0.05       0  5003.8    0.07       0
Bank Sta=4990.8,5003.8
Exp/Cntr=0.3,0.1

Type RM Length L Ch R = 1,2726,472,472,472
BEGIN DESCRIPTION:
Stream0090 5.0
END DESCRIPTION:
XS GIS Cut Line= 3
      1764225.01     13919625.01      1763825.00     13919025.00
      1763674.97     13918874.97
#Sta/Elev= 30
  4278.6 2227.62  4289.9 2226.27  4307.2 2225.25  4322.2 2222.11  4343.2 2220.07
  4358.2 2217.50  4394.3 2215.14  4472.4 2211.72  4508.5 2207.90  4523.5 2207.49
  4544.5 2205.50  4783.4 2195.67  4848.0 2195.06  4935.1 2189.22  4941.1 2189.45
  4985.7 2187.39  4986.2 2186.89  4998.2 2186.89  4998.7 2187.39  5003.3 2187.94
  5013.9 2190.68  5042.2 2199.34  5070.4 2203.99  5084.6 2204.36  5112.9 2206.52
  5127.0 2208.02  5169.4 2214.74  5183.6 2215.64  5197.7 2217.58  5211.9 2218.15
#Mann=4,-1,0
  4278.6     0.1       0  4289.9    0.07       0  4985.7    0.05       0
  4998.7    0.07       0
Bank Sta=4985.7,4998.7
Exp/Cntr=0.3,0.1

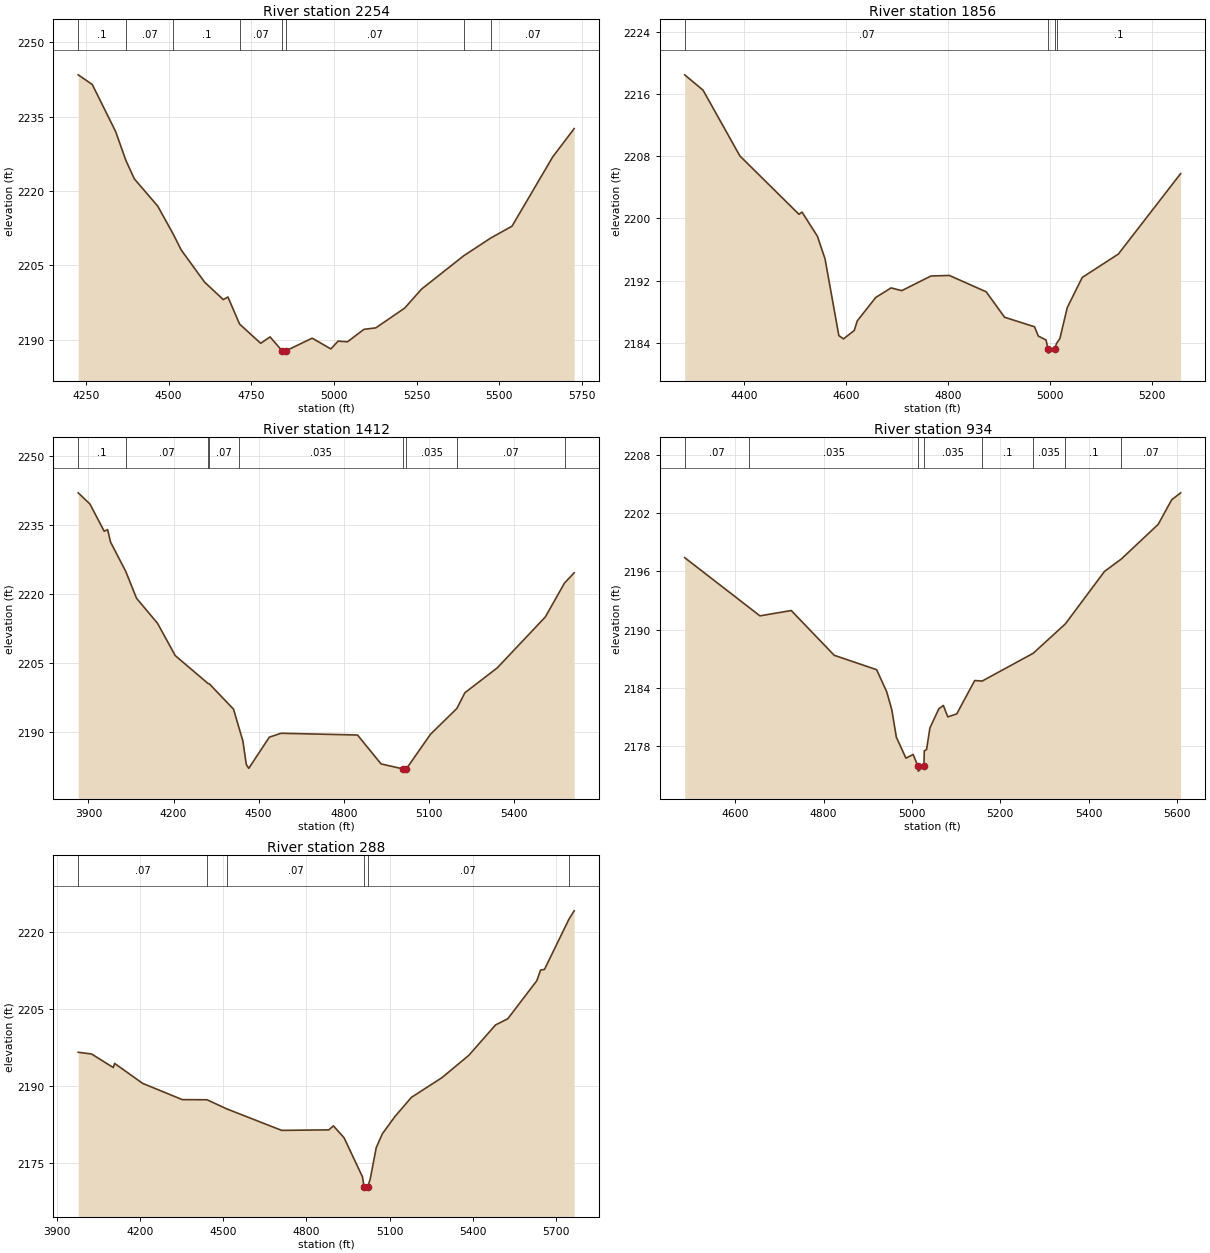
Type RM Length L Ch R = 1,2254,398,398,398
BEGIN DESCRIPTION:
Stream0090 4.0
END DESCRIPTION:
XS GIS Cut Line= 3
      1764775.02     13919375.02      1764225.00     13918825.00
      1763824.98     13918224.97
#Sta/Elev= 30
  4227.0 2243.46  4269.5 2241.51  4340.2 2231.99  4371.4 2226.13  4396.7 2222.44
  4467.4 2216.94  4514.6 2211.24  4538.2 2208.10  4608.9 2201.60  4665.4 2198.06
  4679.6 2198.58  4714.8 2193.12  4778.6 2189.23  4806.9 2190.53  4842.7 2187.75
  4843.2 2187.25  4855.8 2187.75  4934.1 2190.27  4990.7 2188.10  5012.4 2189.67
  5040.9 2189.54  5090.5 2192.05  5126.5 2192.35  5213.7 2196.34  5264.7 2200.18
  5392.2 2206.91  5473.2 2210.47  5538.2 2212.89  5661.4 2226.90  5726.0 2232.59
#Mann=8,-1,0
  4227.0     0.1       0  4371.4    0.07       0  4514.6     0.1       0
  4714.8    0.07       0  4842.7    0.05       0  4855.8    0.07       0
  5392.2     0.1       0  5473.2    0.07       0
Bank Sta=4842.7,4855.8
Exp/Cntr=0.3,0.1

Type RM Length L Ch R = 1,1856,444,444,444
BEGIN DESCRIPTION:
Stream0090 3.0
END DESCRIPTION:
XS GIS Cut Line= 3
      1764774.99     13919124.98      1764375.00     13918525.00
      1764174.99     13918374.99
#Sta/Elev= 30
  4284.3 2218.44  4320.3 2216.47  4392.4 2208.02  4508.1 2200.52  4514.1 2200.80
  4544.2 2197.70  4559.2 2194.78  4586.2 2184.93  4595.3 2184.51  4616.3 2185.59
  4622.3 2186.83  4658.4 2189.83  4688.4 2191.06  4709.4 2190.71  4766.5 2192.59
  4802.6 2192.66  4874.7 2190.56  4910.7 2187.29  4969.3 2186.07  4976.8 2184.87
  4991.9 2184.37  4995.8 2183.18  4996.3 2182.68  5008.9 2183.18  5012.4 2183.92
  5018.9 2184.54  5033.5 2188.54  5062.7 2192.40  5133.5 2195.41  5255.4 2205.75
#Mann=4,-1,0
  4284.3    0.07       0  4995.8    0.05       0  5008.9    0.07       0
  5012.4     0.1       0
Bank Sta=4995.8,5008.9
Exp/Cntr=0.3,0.1

Type RM Length L Ch R = 1,1412,478,478,478
BEGIN DESCRIPTION:
Stream0090 2.0
END DESCRIPTION:
XS GIS Cut Line= 3
      1764925.00     13919275.01      1764625.00     13918175.00
      1764024.97     13918074.99
#Sta/Elev= 30
  3864.0 2242.04  3905.5 2239.59  3955.6 2233.67  3967.7 2234.02  3978.0 2231.31
  4031.5 2224.94  4069.6 2219.07  4143.9 2213.59  4206.1 2206.57  4321.8 2200.50
  4326.6 2200.40  4411.6 2194.90  4430.5 2190.91  4444.5 2188.00  4456.6 2182.86
  4465.2 2182.00  4537.8 2188.80  4579.2 2189.65  4848.7 2189.27  4931.6 2182.98
  5007.8 2181.90  5008.3 2181.40  5020.9 2181.90  5105.6 2189.40  5199.1 2195.07
  5227.2 2198.48  5341.3 2203.89  5511.1 2215.01  5578.5 2222.38  5612.5 2224.62
#Mann=9,-1,0
  3864.0     0.1       0  4031.5    0.07       0  4321.8   0.035       0
  4326.6    0.07       0  4430.5   0.035       0  5007.8   0.035       0
  5020.9   0.035       0  5199.1    0.07       0  5578.5     0.1       0
Bank Sta=5007.8,5020.9
Exp/Cntr=0.3,0.1

Type RM Length L Ch R = 1,934,646,646,646
BEGIN DESCRIPTION:
Stream0090 1.0
END DESCRIPTION:
XS GIS Cut Line= 3
      1765324.96     13918074.98      1764875.00     13917825.00
      1764275.01     13917925.00
#Sta/Elev= 30
  4485.3 2197.43  4631.3 2192.28  4655.7 2191.42  4726.6 2191.97  4823.9 2187.35
  4920.0 2185.86  4942.8 2183.58  4954.3 2181.73  4964.6 2178.90  4986.3 2176.73
  5002.6 2177.11  5013.7 2175.89  5014.2 2175.39  5026.9 2175.89  5027.9 2177.49
  5033.0 2177.61  5040.6 2179.85  5060.9 2181.83  5071.0 2182.17  5081.1 2180.99
  5101.4 2181.30  5142.0 2184.74  5159.0 2184.69  5274.6 2187.56  5347.3 2190.59
  5436.0 2196.01  5474.1 2197.29  5557.6 2200.87  5588.0 2203.40  5608.3 2204.12
#Mann=8,-1,0
  4485.3    0.07       0  4631.3   0.035       0  5013.7   0.035       0
  5026.9   0.035       0  5159.0     0.1       0  5274.6   0.035       0
  5347.3     0.1       0  5474.1    0.07       0
Bank Sta=5013.7,5026.9
Exp/Cntr=0.3,0.1

Type RM Length L Ch R = 1,288,0,0,0
BEGIN DESCRIPTION:
Stream0090 0.0
END DESCRIPTION:
XS GIS Cut Line= 3
      1765457.28     13918022.41      1765317.66     13917384.42
      1764307.31     13916859.41
#Sta/Elev= 30
  3975.4 2196.61  4023.9 2196.27  4101.9 2193.64  4107.0 2194.44  4208.2 2190.55
  4351.5 2187.39  4440.9 2187.36  4511.9 2185.59  4710.4 2181.40  4880.8 2181.50
  4897.3 2182.28  4935.8 2179.97  5002.3 2172.36  5007.9 2170.46  5008.4 2169.96
  5021.3 2170.46  5030.0 2171.83  5052.1 2178.04  5074.2 2180.73  5118.5 2184.02
  5179.2 2187.83  5289.7 2191.67  5386.5 2196.01  5483.1 2201.93  5527.3 2203.13
  5632.3 2210.55  5645.7 2212.60  5660.0 2212.75  5748.1 2222.50  5767.1 2224.15
#Mann=6,-1,0
  3975.4    0.07       0  4440.9     0.1       0  4511.9    0.07       0
  5007.9    0.05       0  5021.3    0.07       0  5748.1     0.1       0
Bank Sta=5007.9,5021.3
Exp/Cntr=0.3,0.1

Chan Stop Cuts=-1