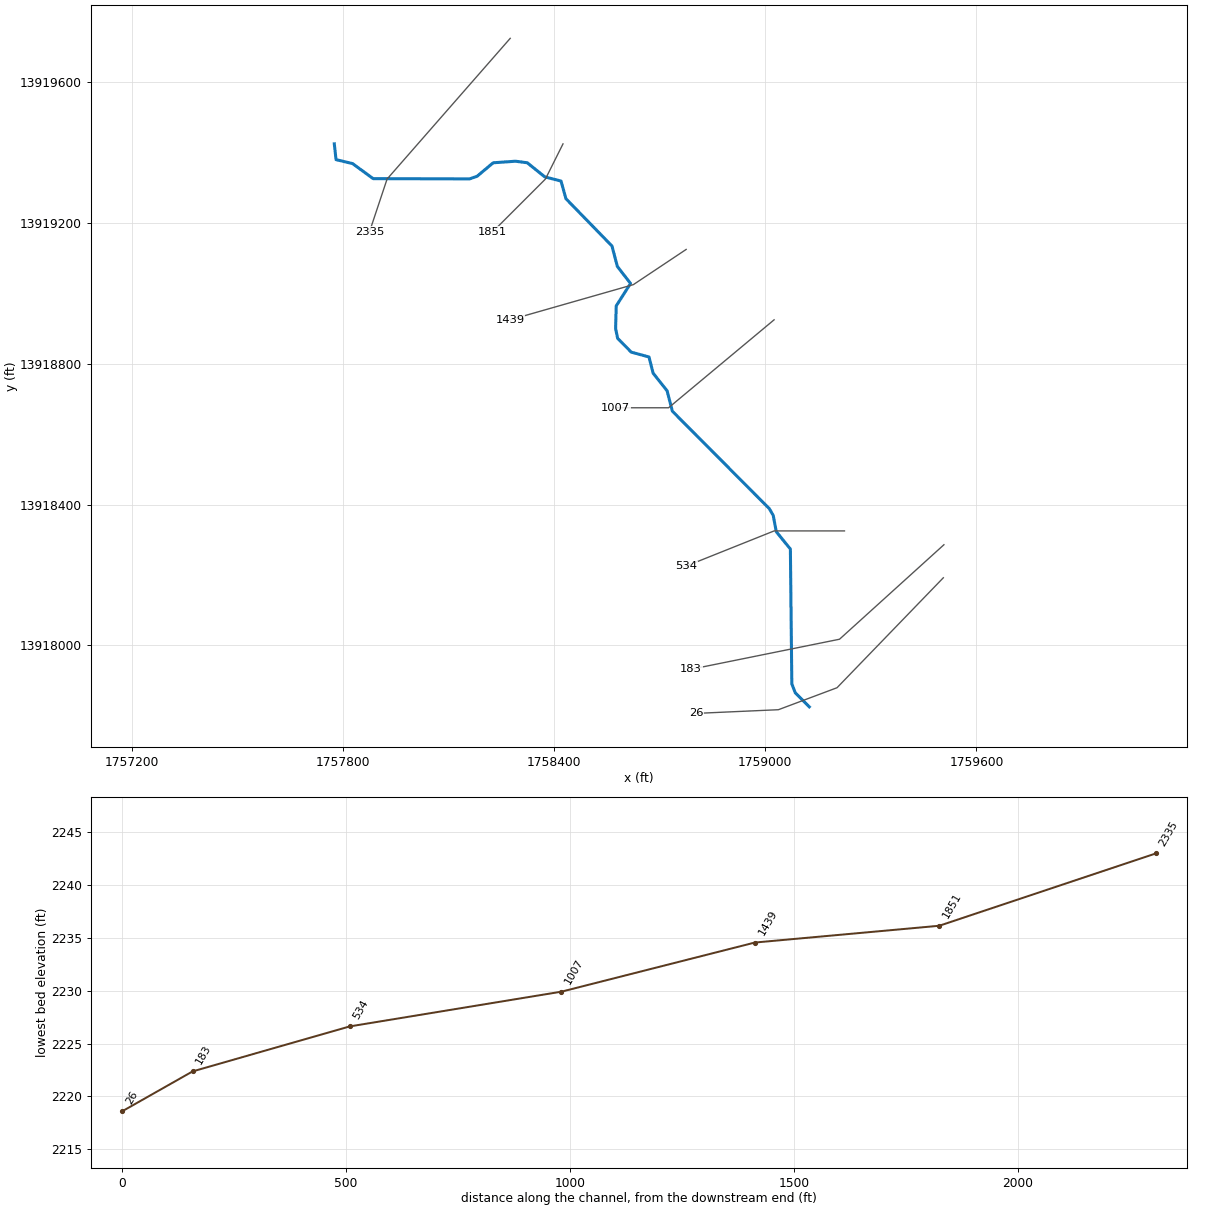
--- Stream0091.prj (project) ---

Proj Title=Stream0091 Base Level Engineering
Current Plan=p01
Default Exp/Contr=0.3,0.1
English Units
Geom File=g01
Flow File=f01
Plan File=p01
BEGIN DESCRIPTION:
Stream0091
END DESCRIPTION:

--- Stream0091.p01 (plan) ---

Plan Title=Multiple Run
Short Identifier=Multiple
Geom File=g01
Flow File=f01
Subcritical Flow
K Sum by GR= 0
Std Step Tol= 0.01
Critical Tol= 0.01
Num of Std Step Trials= 20
Max Error Tol= 0.3
Flow Tol Ratio= 0.001
Split Flow NTrial= 30
Split Flow Tol= 0.02
Split Flow Ratio= 0.02
Log Output Level= 0
Friction Slope Method= 1
Unsteady Friction Slope Method= 2
Unsteady Bridges Friction Slope Method= 1
Parabolic Critical Depth
Global Vel Dist=  1 , 1 , 1
Global Log Level= 0
CheckData=True
Encroach Param= -1, 0, 0, 0
BEGIN DESCRIPTION:
Multiple Run
END DESCRIPTION:

--- Stream0091.f01 (steady flow) ---

Flow Title=Multiple
Number of Profiles=7
Profile Names=10-year,25-year,50-year,1pct_min,100-year,1pct_plu,500-year
River Rch & RM= Stream0091,Reach-1,2335
    1137    1941    2704    1817    3625    7233    6448
River Rch & RM= Stream0091,Reach-1,26
    2409    4266    6087    4180    8341   16642   15508
Boundary for River Rch & Prof#=Stream0091,Reach-1,1
Up Type=0
Dn Type=3
Dn Slope=0.005
Boundary for River Rch & Prof#=Stream0091,Reach-1,2
Up Type=0
Dn Type=3
Dn Slope=0.005
Boundary for River Rch & Prof#=Stream0091,Reach-1,3
Up Type=0
Dn Type=3
Dn Slope=0.005
Boundary for River Rch & Prof#=Stream0091,Reach-1,4
Up Type=0
Dn Type=3
Dn Slope=0.005
Boundary for River Rch & Prof#=Stream0091,Reach-1,5
Up Type=0
Dn Type=3
Dn Slope=0.005
Boundary for River Rch & Prof#=Stream0091,Reach-1,6
Up Type=0
Dn Type=3
Dn Slope=0.005
Boundary for River Rch & Prof#=Stream0091,Reach-1,7
Up Type=0
Dn Type=3
Dn Slope=0.005

--- Stream0091.g01 (geometry) ---

Geom Title=Existing Conditions

River Reach=Stream0091,Reach-1
Reach XY= 30
      1757775.00     13919425.00      1757779.90     13919380.28
      1757827.00     13919368.96      1757885.48     13919326.18
      1758159.78     13919325.52      1758181.06     13919333.15
      1758226.60     13919371.30      1758290.07     13919375.72
      1758323.44     13919371.34      1758373.16     13919331.28
      1758419.39     13919319.41      1758433.28     13919269.25
      1758564.25     13919134.68      1758579.45     13919076.65
      1758616.96     13919028.32      1758576.26     13918964.51
      1758574.49     13918899.88      1758580.33     13918872.34
      1758618.91     13918833.15      1758669.37     13918819.38
      1758681.24     13918773.14      1758720.82     13918723.29
      1758735.77     13918665.32      1759011.38     13918388.22
      1759022.50     13918368.97      1759031.14     13918322.83
      1759071.25     13918273.45      1759075.36     13917890.15
      1759085.05     13917865.02      1759125.00     13917825.00

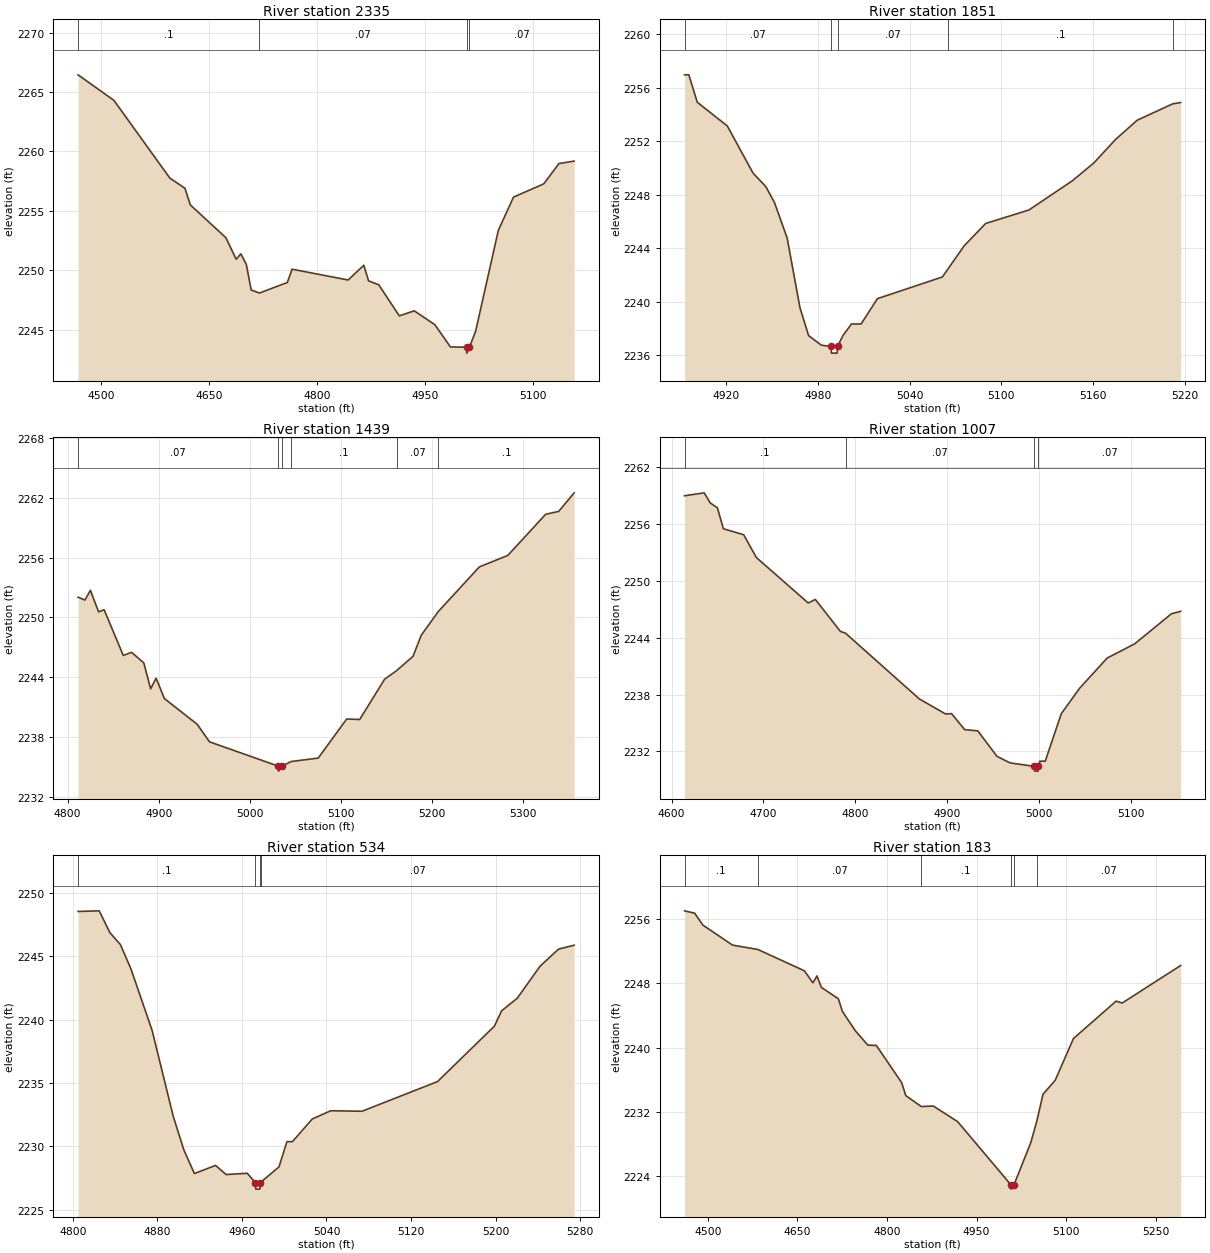
Type RM Length L Ch R = 1,2335,484,484,484
BEGIN DESCRIPTION:
Stream0091 5.0
END DESCRIPTION:
XS GIS Cut Line= 3
      1758274.99     13919724.99      1757925.00     13919325.00
      1757875.00     13919175.00
#Sta/Elev= 30
  4468.1 2266.45  4517.9 2264.30  4595.7 2257.75  4616.6 2256.90  4624.2 2255.49
  4673.6 2252.73  4687.8 2250.92  4694.4 2251.37  4702.0 2250.48  4708.7 2248.33
  4720.2 2248.07  4759.0 2248.96  4765.6 2250.08  4843.5 2249.17  4865.3 2250.41
  4871.9 2249.10  4886.2 2248.76  4914.6 2246.15  4935.5 2246.57  4964.0 2245.41
  4985.8 2243.53  5008.1 2243.51  5008.4 2243.01  5012.1 2243.51  5020.7 2244.84
  5052.3 2253.35  5073.4 2256.15  5115.5 2257.27  5136.6 2258.98  5157.7 2259.18
#Mann=4,-1,0
  4468.1     0.1       0  4720.2    0.07       0  5008.1    0.05       0
  5012.1    0.07       0
Bank Sta=5008.1,5012.1
Exp/Cntr=0.3,0.1

Type RM Length L Ch R = 1,1851,412,412,412
BEGIN DESCRIPTION:
Stream0091 4.0
END DESCRIPTION:
XS GIS Cut Line= 3
      1758424.98     13919424.97      1758375.00     13919325.00
      1758225.00     13919175.00
#Sta/Elev= 30
  4893.1 2256.96  4895.9 2256.96  4901.4 2254.91  4921.0 2253.14  4937.8 2249.62
  4946.2 2248.60  4951.8 2247.42  4960.1 2244.76  4968.5 2239.53  4974.1 2237.47
  4982.5 2236.75  4988.8 2236.66  4989.0 2236.16  4992.7 2236.16  4993.0 2236.66
  4996.5 2237.47  5002.1 2238.34  5008.4 2238.34  5019.0 2240.23  5061.4 2241.85
  5065.1 2242.45  5075.6 2244.17  5089.7 2245.85  5118.0 2246.86  5146.3 2249.04
  5160.4 2250.38  5174.6 2252.14  5188.7 2253.57  5211.8 2254.79  5217.0 2254.89
#Mann=5,-1,0
  4893.1    0.07       0  4988.8    0.05       0  4993.0    0.07       0
  5065.1     0.1       0  5211.8    0.07       0
Bank Sta=4988.8,4993
Exp/Cntr=0.3,0.1

Type RM Length L Ch R = 1,1439,432,432,432
BEGIN DESCRIPTION:
Stream0091 3.0
END DESCRIPTION:
XS GIS Cut Line= 3
      1758775.01     13919125.01      1758625.00     13919025.00
      1758275.00     13918925.00
#Sta/Elev= 30
  4811.5 2252.02  4819.0 2251.73  4825.0 2252.71  4834.0 2250.55  4840.1 2250.76
  4861.1 2246.17  4870.1 2246.49  4883.6 2245.43  4891.1 2242.83  4897.1 2243.89
  4906.2 2241.85  4942.2 2239.27  4955.7 2237.51  5031.2 2235.07  5031.5 2234.57
  5035.5 2235.07  5045.1 2235.53  5075.0 2235.88  5106.2 2239.80  5120.5 2239.75
  5147.8 2243.79  5161.1 2244.66  5179.0 2246.09  5188.1 2248.21  5206.8 2250.59
  5251.8 2255.06  5283.0 2256.21  5324.6 2260.34  5338.9 2260.63  5355.8 2262.49
#Mann=6,-1,0
  4811.5    0.07       0  5031.2    0.05       0  5035.5    0.07       0
  5045.1     0.1       0  5161.1    0.07       0  5206.8     0.1       0
Bank Sta=5031.2,5035.5
Exp/Cntr=0.3,0.1

Type RM Length L Ch R = 1,1007,473,473,473
BEGIN DESCRIPTION:
Stream0091 2.0
END DESCRIPTION:
XS GIS Cut Line= 3
      1759024.98     13918924.98      1758725.00     13918675.00
      1758574.98     13918675.00
#Sta/Elev= 30
  4614.1 2258.97  4635.5 2259.28  4642.1 2258.21  4649.9 2257.70  4656.4 2255.49
  4678.5 2254.86  4692.2 2252.47  4748.8 2247.66  4756.6 2248.03  4783.9 2244.66
  4789.5 2244.47  4869.9 2237.54  4898.5 2235.95  4905.0 2235.99  4919.3 2234.30
  4933.6 2234.17  4954.5 2231.48  4968.8 2230.79  4995.3 2230.42  4995.6 2229.92
  4999.3 2229.92  4999.6 2230.42  5001.3 2230.97  5007.1 2230.97  5024.6 2235.98
  5044.6 2238.67  5074.6 2241.85  5104.6 2243.35  5144.6 2246.52  5154.6 2246.78
#Mann=4,-1,0
  4614.1     0.1       0  4789.5    0.07       0  4995.3    0.05       0
  4999.6    0.07       0
Bank Sta=4995.3,4999.6
Exp/Cntr=0.3,0.1

Type RM Length L Ch R = 1,534,351,351,351
BEGIN DESCRIPTION:
Stream0091 1.0
END DESCRIPTION:
XS GIS Cut Line= 3
      1759224.98     13918325.00      1759025.00     13918325.00
      1758775.03     13918225.01
#Sta/Elev= 30
  4805.1 2248.52  4825.1 2248.57  4835.1 2246.86  4845.1 2245.91  4855.1 2243.99
  4875.1 2239.15  4895.1 2232.37  4905.1 2229.73  4915.1 2227.86  4935.1 2228.50
  4945.1 2227.78  4965.1 2227.88  4972.9 2227.13  4973.2 2226.63  4977.0 2226.63
  4977.3 2227.13  4977.7 2227.16  4995.1 2228.38  5002.6 2230.37  5007.8 2230.37
  5026.6 2232.16  5044.1 2232.81  5073.7 2232.77  5145.1 2235.11  5198.9 2239.48
  5205.7 2240.69  5220.5 2241.68  5242.0 2244.20  5259.5 2245.55  5274.3 2245.86
#Mann=4,-1,0
  4805.1     0.1       0  4972.9    0.05       0  4977.3     0.1       0
  4977.7    0.07       0
Bank Sta=4972.9,4977.3
Exp/Cntr=0.3,0.1

Type RM Length L Ch R = 1,183,157,157,157
BEGIN DESCRIPTION:
Stream0091 0.0
END DESCRIPTION:
XS GIS Cut Line= 3
      1759507.68     13918285.76      1759210.93     13918017.17
      1758789.13     13917931.82
#Sta/Elev= 30
  4461.0 2257.02  4477.9 2256.73  4491.6 2255.25  4541.4 2252.75  4583.7 2252.21
  4661.7 2249.55  4675.9 2248.05  4682.7 2248.91  4690.1 2247.49  4718.5 2246.07
  4725.3 2244.50  4746.9 2242.09  4767.9 2240.30  4782.1 2240.26  4824.6 2235.62
  4831.4 2234.02  4857.4 2232.65  4877.5 2232.72  4918.3 2230.77  5007.9 2222.87
  5008.2 2222.37  5012.4 2222.87  5040.8 2228.17  5051.1 2230.92  5061.2 2234.18
  5081.6 2235.92  5112.2 2241.12  5183.6 2245.78  5193.8 2245.54  5291.6 2250.21
#Mann=6,-1,0
  4461.0     0.1       0  4583.7    0.07       0  4857.4     0.1       0
  5007.9    0.05       0  5012.4     0.1       0  5051.1    0.07       0
Bank Sta=5007.9,5012.4
Exp/Cntr=0.3,0.1

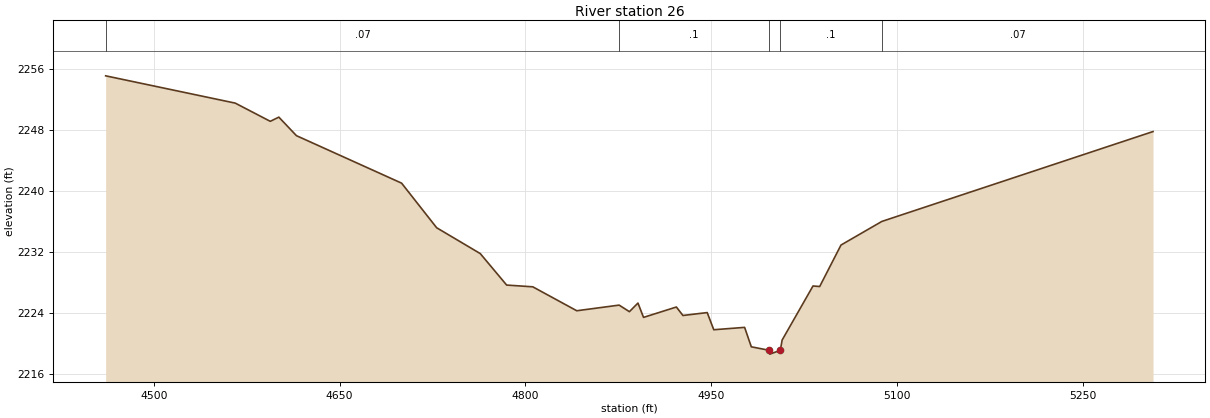
Type RM Length L Ch R = 1,26,0,0,0
BEGIN DESCRIPTION:
Stream0091 T
END DESCRIPTION:
XS GIS Cut Line= 4
      1759505.92     13918191.82      1759203.85     13917879.33
      1759037.18     13917816.83      1758804.54     13917806.42
#Sta/Elev= 30
  4461.2 2255.11  4565.8 2251.53  4594.1 2249.14  4601.0 2249.69  4615.2 2247.26
  4700.1 2241.03  4728.4 2235.18  4763.6 2231.79  4784.9 2227.66  4806.0 2227.43
  4841.5 2224.29  4875.7 2225.03  4884.0 2224.17  4890.9 2225.30  4895.4 2223.42
  4921.9 2224.78  4927.2 2223.67  4946.8 2224.05  4952.1 2221.80  4977.0 2222.11
  4982.4 2219.56  4996.9 2219.10  4997.4 2218.60  5005.8 2219.10  5007.3 2220.45
  5032.2 2227.54  5037.6 2227.47  5054.8 2232.91  5087.8 2236.01  5306.7 2247.80
#Mann=5,-1,0
  4461.2    0.07       0  4875.7     0.1       0  4996.9    0.05       0
  5005.8     0.1       0  5087.8    0.07       0
Bank Sta=4996.9,5005.8
Exp/Cntr=0.3,0.1

Chan Stop Cuts=-1