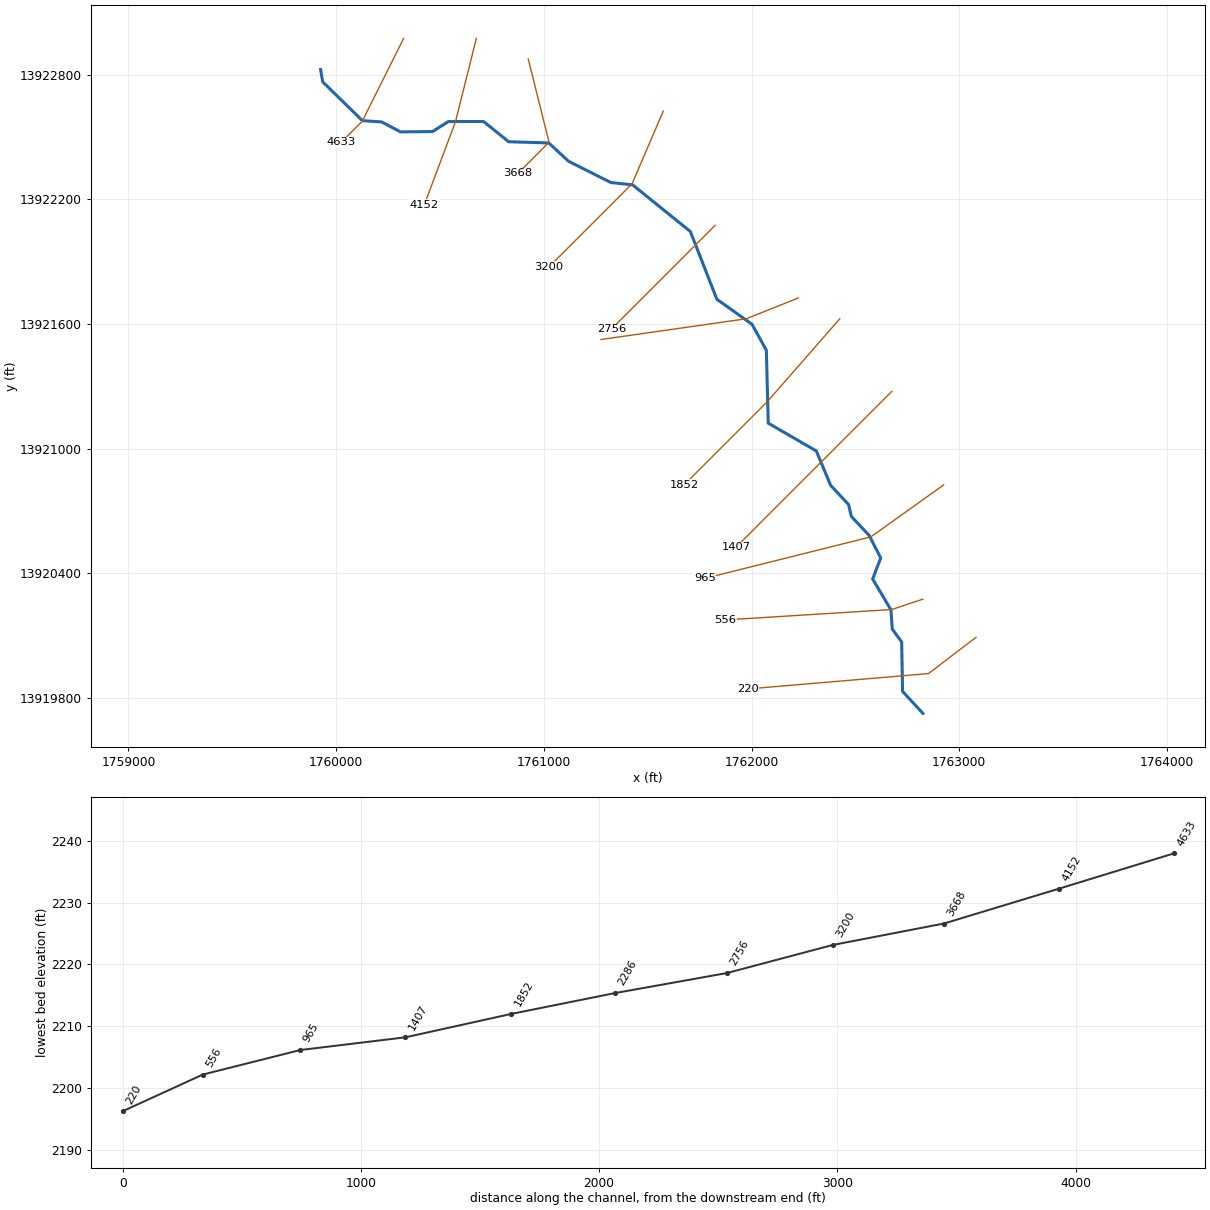
--- Stream0092.prj (project) ---

Proj Title=Stream0092 Base Level Engineering
Current Plan=p01
Default Exp/Contr=0.3,0.1
English Units
Geom File=g01
Flow File=f01
Plan File=p01
BEGIN DESCRIPTION:
Stream0092
END DESCRIPTION:

--- Stream0092.p01 (plan) ---

Plan Title=Multiple Run
Short Identifier=Multiple
Geom File=g01
Flow File=f01
Subcritical Flow
K Sum by GR= 0
Std Step Tol= 0.01
Critical Tol= 0.01
Num of Std Step Trials= 20
Max Error Tol= 0.3
Flow Tol Ratio= 0.001
Split Flow NTrial= 30
Split Flow Tol= 0.02
Split Flow Ratio= 0.02
Log Output Level= 0
Friction Slope Method= 1
Unsteady Friction Slope Method= 2
Unsteady Bridges Friction Slope Method= 1
Parabolic Critical Depth
Global Vel Dist=  1 , 1 , 1
Global Log Level= 0
CheckData=True
Encroach Param= -1, 0, 0, 0
BEGIN DESCRIPTION:
Multiple Run
END DESCRIPTION:

--- Stream0092.f01 (steady flow) ---

Flow Title=Multiple
Number of Profiles=7
Profile Names=10-year,25-year,50-year,1pct_min,100-year,1pct_plu,500-year
River Rch & RM= Stream0092,Reach-1,4633
    1355    2339    3284    2223    4436    8851    8011
Boundary for River Rch & Prof#=Stream0092,Reach-1,1
Up Type=0
Dn Type=3
Dn Slope=0.005
Boundary for River Rch & Prof#=Stream0092,Reach-1,2
Up Type=0
Dn Type=3
Dn Slope=0.005
Boundary for River Rch & Prof#=Stream0092,Reach-1,3
Up Type=0
Dn Type=3
Dn Slope=0.005
Boundary for River Rch & Prof#=Stream0092,Reach-1,4
Up Type=0
Dn Type=3
Dn Slope=0.005
Boundary for River Rch & Prof#=Stream0092,Reach-1,5
Up Type=0
Dn Type=3
Dn Slope=0.005
Boundary for River Rch & Prof#=Stream0092,Reach-1,6
Up Type=0
Dn Type=3
Dn Slope=0.005
Boundary for River Rch & Prof#=Stream0092,Reach-1,7
Up Type=0
Dn Type=3
Dn Slope=0.005

--- Stream0092.g01 (geometry) ---

Geom Title=Existing Conditions

River Reach=Stream0092,Reach-1
Reach XY= 30
      1759925.00     13922825.00      1759935.51     13922765.21
      1760126.50     13922578.61      1760219.02     13922572.64
      1760309.82     13922524.57      1760464.49     13922526.22
      1760540.22     13922574.48      1760709.84     13922574.61
      1760830.86     13922477.07      1761023.53     13922471.45
      1761118.95     13922383.16      1761322.68     13922280.77
      1761427.42     13922269.46      1761705.22     13922045.09
      1761833.02     13921718.66      1762002.01     13921598.52
      1762071.25     13921473.45      1762080.36     13921122.30
      1762311.53     13920988.57      1762380.85     13920822.71
      1762466.82     13920731.04      1762480.87     13920672.72
      1762566.85     13920581.05      1762621.63     13920473.27
      1762583.07     13920371.69      1762671.17     13920223.42
      1762677.36     13920130.98      1762722.74     13920069.06
      1762727.02     13919830.84      1762825.00     13919725.00

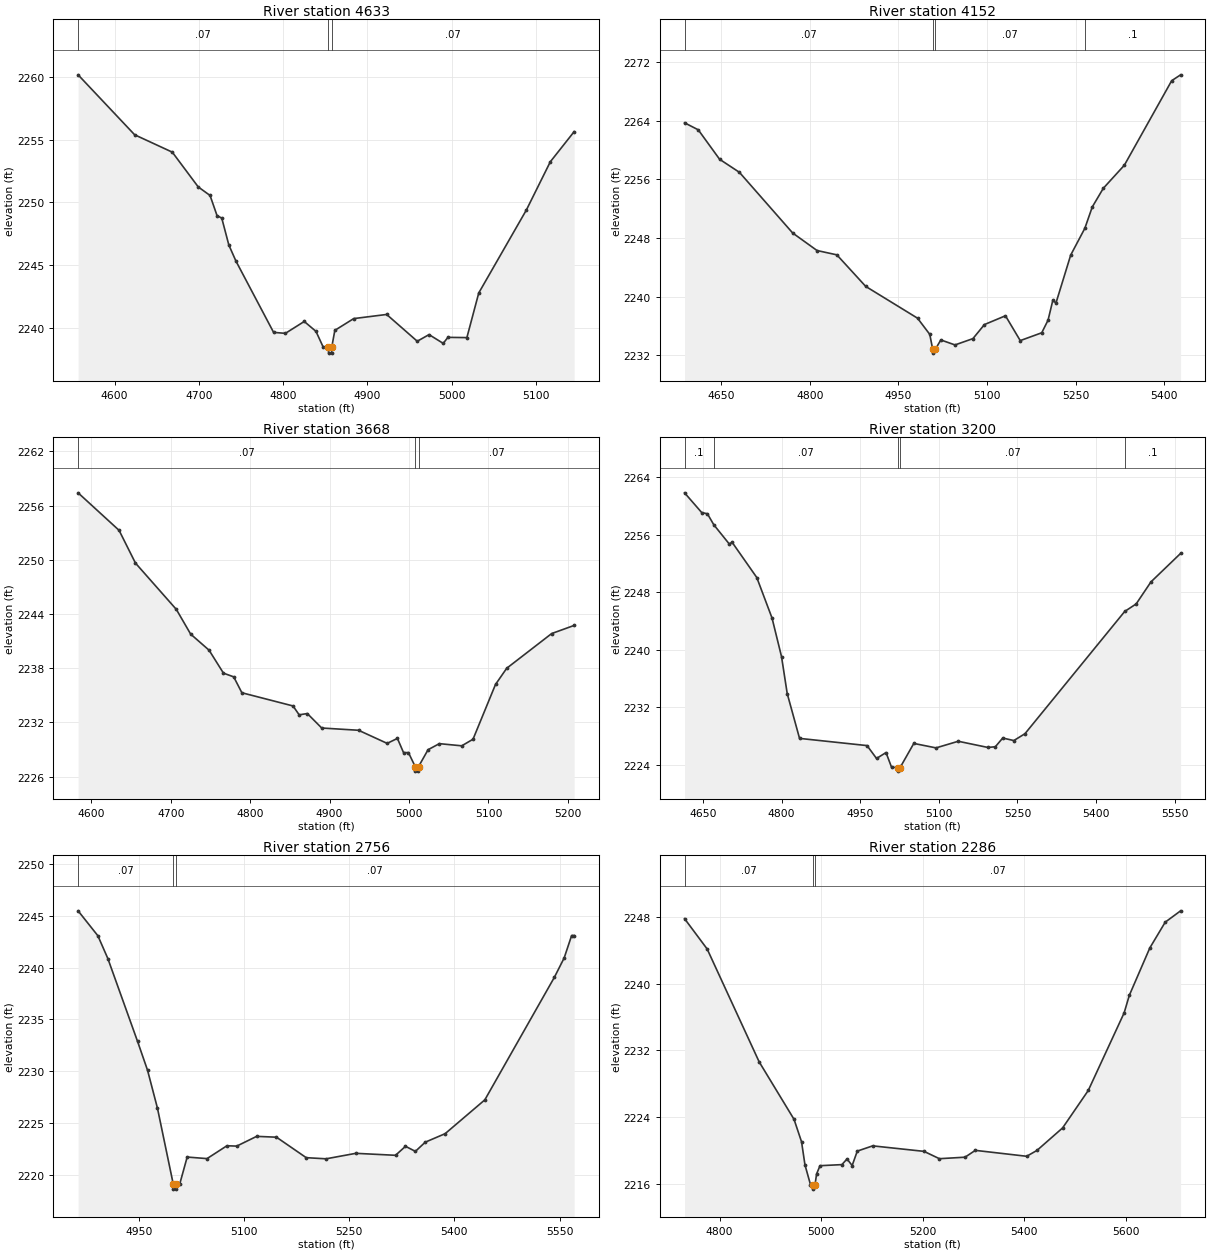
Type RM Length L Ch R = 1,4633,481,481,481
BEGIN DESCRIPTION:
Stream0092 10.0
END DESCRIPTION:
XS GIS Cut Line= 3
      1760325.01     13922975.02      1760125.00     13922575.00
      1760024.97     13922474.97
#Sta/Elev= 30
  4556.7 2260.20  4623.8 2255.41  4668.5 2254.02  4699.3 2251.24  4713.3 2250.56
  4721.6 2248.95  4727.2 2248.75  4735.6 2246.60  4744.0 2245.32  4788.7 2239.62
  4802.7 2239.54  4825.1 2240.49  4839.0 2239.70  4847.4 2238.47  4853.7 2238.46
  4854.0 2237.96  4857.6 2237.96  4857.8 2238.46  4861.4 2239.78  4883.8 2240.72
  4922.9 2241.05  4959.2 2238.91  4973.2 2239.44  4990.0 2238.74  4995.6 2239.22
  5018.1 2239.20  5032.2 2242.77  5088.8 2249.41  5117.1 2253.25  5145.4 2255.66
#Mann=3,-1,0
  4556.7    0.07       0  4853.7    0.05       0  4857.8    0.07       0
Bank Sta=4853.7,4857.8
Exp/Cntr=0.3,0.1

Type RM Length L Ch R = 1,4152,484,484,484
BEGIN DESCRIPTION:
Stream0092 9.0
END DESCRIPTION:
XS GIS Cut Line= 3
      1760675.00     13922974.99      1760575.00     13922575.00
      1760425.00     13922175.00
#Sta/Elev= 30
  4588.1 2263.72  4611.3 2262.76  4647.4 2258.74  4680.9 2256.96  4771.1 2248.67
  4812.3 2246.28  4845.8 2245.69  4894.7 2241.38  4982.4 2237.04  5003.1 2234.83
  5008.1 2232.77  5008.4 2232.27  5012.3 2232.77  5021.8 2234.07  5045.8 2233.39
  5076.1 2234.25  5095.6 2236.17  5131.2 2237.37  5156.2 2233.98  5192.6 2235.05
  5203.3 2236.78  5211.3 2239.47  5216.7 2239.12  5241.6 2245.66  5265.5 2249.31
  5278.1 2252.23  5296.8 2254.78  5332.4 2257.93  5412.5 2269.47  5427.6 2270.27
#Mann=4,-1,0
  4588.1    0.07       0  5008.1    0.05       0  5012.3    0.07       0
  5265.5     0.1       0
Bank Sta=5008.1,5012.3
Exp/Cntr=0.3,0.1

Type RM Length L Ch R = 1,3668,468,468,468
BEGIN DESCRIPTION:
Stream0092 8.0
END DESCRIPTION:
XS GIS Cut Line= 3
      1760925.00     13922875.01      1761025.00     13922475.00
      1760874.97     13922324.97
#Sta/Elev= 30
  4583.4 2257.41  4635.0 2253.26  4655.6 2249.64  4707.1 2244.51  4725.1 2241.78
  4748.3 2240.00  4766.4 2237.46  4779.3 2237.05  4789.6 2235.29  4854.0 2233.83
  4861.7 2232.85  4872.0 2232.99  4890.1 2231.39  4936.5 2231.14  4972.5 2229.69
  4985.4 2230.24  4993.1 2228.67  4999.3 2228.67  5007.8 2227.12  5008.0 2226.62
  5011.7 2226.62  5012.0 2227.12  5024.0 2228.99  5038.2 2229.66  5066.4 2229.42
  5080.6 2230.15  5108.9 2236.21  5123.0 2238.00  5179.6 2241.84  5207.9 2242.74
#Mann=3,-1,0
  4583.4    0.07       0  5007.8    0.05       0  5012.0    0.07       0
Bank Sta=5007.8,5012
Exp/Cntr=0.3,0.1

Type RM Length L Ch R = 1,3200,444,444,444
BEGIN DESCRIPTION:
Stream0092 7.0
END DESCRIPTION:
XS GIS Cut Line= 3
      1761575.02     13922625.04      1761425.00     13922275.00
      1761025.01     13921875.01
#Sta/Elev= 30
  4614.8 2261.82  4647.5 2259.08  4658.4 2258.91  4670.6 2257.38  4700.1 2254.71
  4705.5 2254.95  4752.6 2250.05  4781.7 2244.42  4799.8 2239.06  4810.7 2233.91
  4834.2 2227.69  4963.0 2226.69  4981.1 2224.90  4999.2 2225.72  5009.8 2223.67
  5021.7 2223.64  5022.0 2223.14  5026.1 2223.64  5052.2 2226.99  5094.6 2226.37
  5137.0 2227.29  5193.6 2226.43  5207.8 2226.53  5221.9 2227.74  5243.1 2227.39
  5264.3 2228.34  5454.6 2245.33  5476.5 2246.38  5504.7 2249.44  5561.3 2253.40
#Mann=5,-1,0
  4614.8     0.1       0  4670.6    0.07       0  5021.7    0.05       0
  5026.1    0.07       0  5454.6     0.1       0
Bank Sta=5021.7,5026.1
Exp/Cntr=0.3,0.1

Type RM Length L Ch R = 1,2756,470,470,470
BEGIN DESCRIPTION:
Stream0092 6.0
END DESCRIPTION:
XS GIS Cut Line= 3
      1761824.97     13922074.97      1761725.00     13921975.00
      1761324.98     13921574.98
#Sta/Elev= 30
  4863.7 2245.50  4891.9 2243.09  4906.1 2240.89  4948.5 2232.87  4962.7 2230.09
  4976.8 2226.43  4999.3 2219.10  4999.6 2218.60  5003.4 2218.60  5003.7 2219.10
  5008.6 2219.10  5019.2 2221.70  5047.5 2221.55  5075.8 2222.79  5089.9 2222.76
  5118.2 2223.70  5146.5 2223.62  5188.9 2221.64  5217.2 2221.53  5259.6 2222.06
  5316.2 2221.87  5330.4 2222.74  5344.5 2222.25  5358.6 2223.14  5386.9 2223.96
  5443.5 2227.23  5542.5 2239.06  5556.6 2240.95  5567.2 2243.11  5570.8 2243.11
#Mann=3,-1,0
  4863.7    0.07       0  4999.3    0.05       0  5003.7    0.07       0
Bank Sta=4999.3,5003.7
Exp/Cntr=0.3,0.1

Type RM Length L Ch R = 1,2286,434,434,434
BEGIN DESCRIPTION:
Stream0092 5.0
END DESCRIPTION:
XS GIS Cut Line= 3
      1762225.04     13921725.02      1761975.00     13921625.00
      1761275.01     13921525.00
#Sta/Elev= 30
  4731.2 2247.80  4775.7 2244.16  4878.0 2230.63  4946.7 2223.73  4961.5 2221.03
  4968.2 2218.27  4979.0 2215.91  4983.5 2215.86  4983.8 2215.36  4987.9 2215.86
  4991.1 2217.18  4997.8 2218.17  5040.9 2218.30  5051.0 2218.98  5061.1 2218.19
  5071.2 2219.92  5101.5 2220.55  5202.5 2219.89  5232.8 2219.01  5283.3 2219.19
  5303.5 2220.01  5404.6 2219.30  5424.8 2220.00  5475.3 2222.70  5525.8 2227.19
  5596.5 2236.51  5606.6 2238.60  5647.0 2244.29  5677.3 2247.38  5707.6 2248.74
#Mann=3,-1,0
  4731.2    0.07       0  4983.5    0.05       0  4987.9    0.07       0
Bank Sta=4983.5,4987.9
Exp/Cntr=0.3,0.1

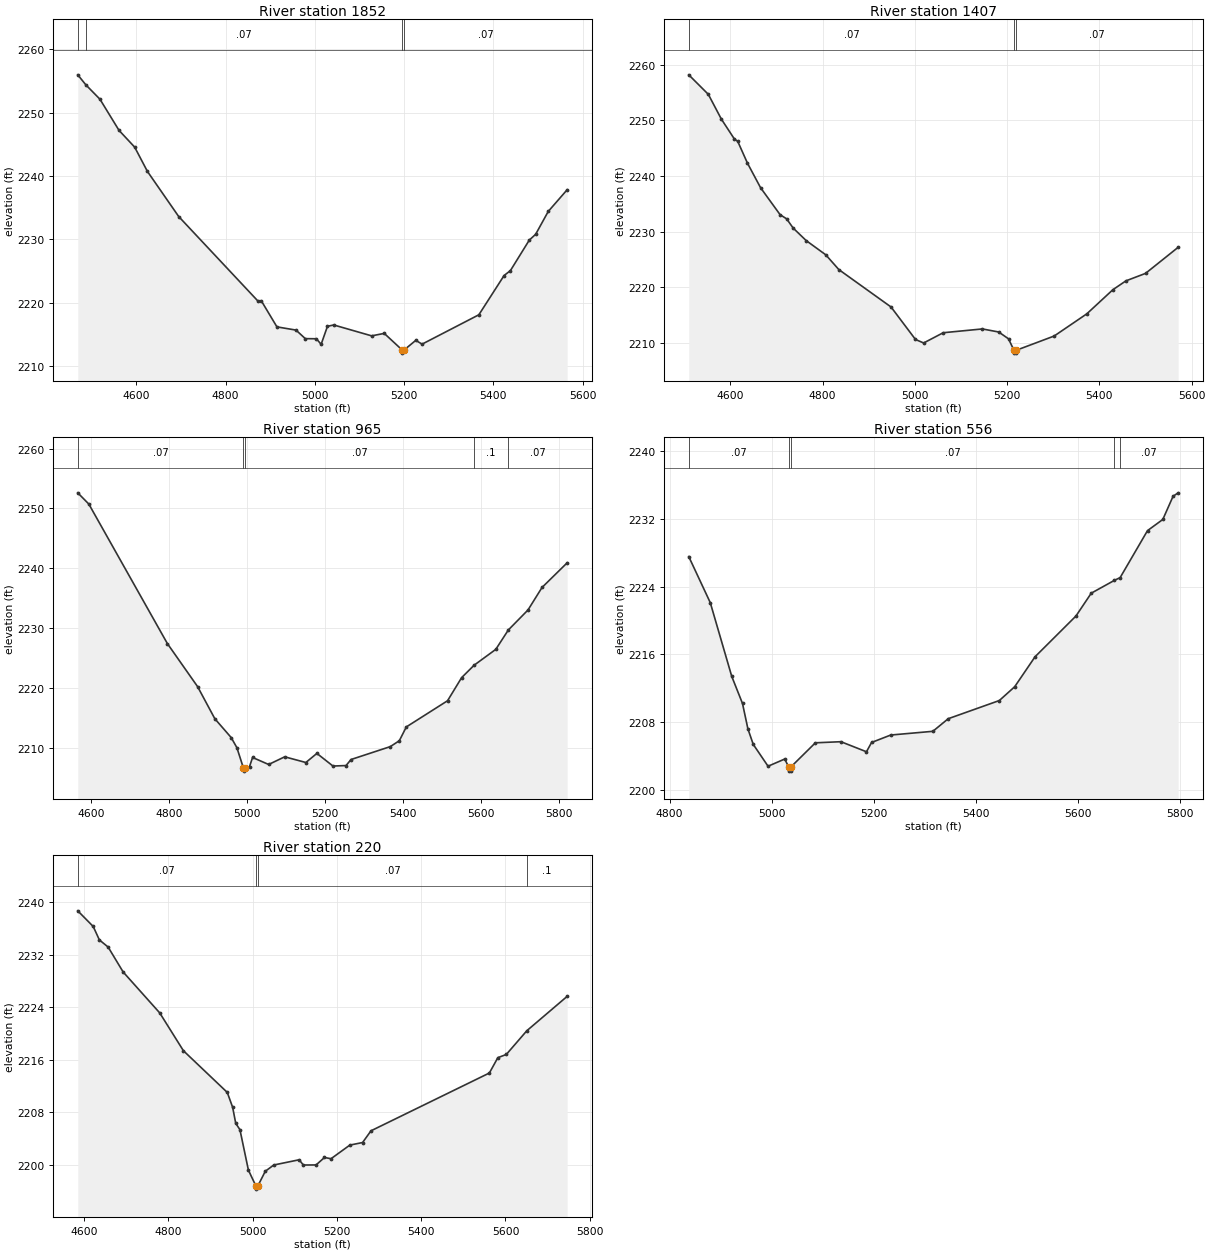
Type RM Length L Ch R = 1,1852,445,445,445
BEGIN DESCRIPTION:
Stream0092 4.0
END DESCRIPTION:
XS GIS Cut Line= 3
      1762424.99     13921624.98      1762075.00     13921225.00
      1761674.98     13920824.98
#Sta/Elev= 30
  4468.4 2255.99  4486.5 2254.41  4518.2 2252.13  4560.9 2247.21  4596.0 2244.56
  4624.5 2240.73  4694.7 2233.59  4872.2 2220.24  4879.8 2220.28  4914.9 2216.15
  4957.7 2215.64  4978.5 2214.29  5003.4 2214.27  5014.0 2213.39  5028.2 2216.24
  5042.3 2216.45  5127.2 2214.73  5155.5 2215.12  5195.6 2212.50  5195.9 2212.00
  5200.1 2212.50  5226.2 2214.02  5240.3 2213.42  5367.6 2218.06  5424.2 2224.27
  5438.3 2225.04  5480.7 2229.87  5494.9 2230.78  5523.1 2234.39  5565.6 2237.83
#Mann=4,-1,0
  4468.4     0.1       0  4486.5    0.07       0  5195.6    0.05       0
  5200.1    0.07       0
Bank Sta=5195.6,5200.1
Exp/Cntr=0.3,0.1

Type RM Length L Ch R = 1,1407,442,442,442
BEGIN DESCRIPTION:
Stream0092 3.0
END DESCRIPTION:
XS GIS Cut Line= 3
      1762675.00     13921275.00      1762325.00     13920925.00
      1761924.97     13920524.97
#Sta/Elev= 30
  4510.1 2258.15  4552.5 2254.65  4580.8 2250.20  4609.1 2246.62  4616.2 2246.22
  4637.4 2242.29  4665.7 2237.90  4708.1 2233.05  4722.2 2232.31  4736.4 2230.65
  4764.7 2228.40  4807.1 2225.85  4835.4 2223.20  4948.5 2216.49  5001.5 2210.66
  5019.2 2210.03  5061.6 2211.87  5146.5 2212.55  5181.9 2212.00  5203.1 2210.78
  5215.0 2208.71  5215.3 2208.21  5219.2 2208.21  5219.5 2208.71  5302.1 2211.28
  5372.8 2215.26  5429.3 2219.59  5457.6 2221.18  5500.1 2222.52  5570.8 2227.20
#Mann=3,-1,0
  4510.1    0.07       0  5215.0    0.05       0  5219.5    0.07       0
Bank Sta=5215,5219.5
Exp/Cntr=0.3,0.1

Type RM Length L Ch R = 1,965,409,409,409
BEGIN DESCRIPTION:
Stream0092 2.0
END DESCRIPTION:
XS GIS Cut Line= 3
      1762925.02     13920825.01      1762575.00     13920575.00
      1761774.96     13920374.99
#Sta/Elev= 30
  4565.5 2252.61  4593.8 2250.74  4795.3 2227.44  4872.7 2220.26  4917.0 2214.89
  4958.8 2211.76  4973.5 2210.06  4990.3 2206.65  4990.6 2206.15  4994.8 2206.65
  5005.9 2206.91  5013.7 2208.43  5054.9 2207.26  5096.1 2208.54  5150.3 2207.59
  5178.6 2209.11  5219.8 2207.00  5253.3 2207.08  5266.2 2208.09  5366.7 2210.24
  5389.9 2211.22  5407.9 2213.53  5513.6 2217.90  5549.7 2221.76  5581.7 2223.83
  5637.3 2226.48  5669.4 2229.71  5719.8 2233.05  5755.8 2236.81  5820.3 2240.93
#Mann=5,-1,0
  4565.5    0.07       0  4990.3    0.05       0  4994.8    0.07       0
  5581.7     0.1       0  5669.4    0.07       0
Bank Sta=4990.3,4994.8
Exp/Cntr=0.3,0.1

Type RM Length L Ch R = 1,556,336,336,336
BEGIN DESCRIPTION:
Stream0092 1.0
END DESCRIPTION:
XS GIS Cut Line= 3
      1762825.00     13920275.00      1762675.00     13920225.00
      1761874.98     13920175.00
#Sta/Elev= 30
  4837.4 2227.56  4879.6 2222.11  4921.7 2213.39  4942.8 2210.18  4953.4 2207.18
  4963.9 2205.34  4992.9 2202.76  5025.6 2203.61  5033.3 2202.68  5033.6 2202.18
  5037.5 2202.18  5037.8 2202.68  5085.7 2205.53  5135.8 2205.66  5185.9 2204.47
  5195.9 2205.57  5233.5 2206.45  5316.1 2206.89  5346.2 2208.38  5446.4 2210.53
  5476.5 2212.16  5516.5 2215.71  5596.7 2220.53  5626.7 2223.23  5672.2 2224.75
  5683.3 2225.07  5737.0 2230.63  5767.0 2231.95  5787.1 2234.69  5797.1 2235.10
#Mann=5,-1,0
  4837.4    0.07       0  5033.3    0.05       0  5037.8    0.07       0
  5672.2     0.1       0  5683.3    0.07       0
Bank Sta=5033.3,5037.8
Exp/Cntr=0.3,0.1

Type RM Length L Ch R = 1,220,0,0,0
BEGIN DESCRIPTION:
Stream0092 0.0
END DESCRIPTION:
XS GIS Cut Line= 3
      1763080.64     13920091.19      1762851.86     13919916.59
      1761981.00     13919842.54
#Sta/Elev= 30
  4584.7 2238.72  4621.4 2236.33  4636.0 2234.28  4656.8 2233.19  4692.4 2229.39
  4779.3 2223.14  4835.5 2217.37  4939.6 2211.01  4952.4 2208.73  4959.7 2206.29
  4969.7 2205.32  4989.8 2199.15  5007.4 2196.75  5007.7 2196.25  5012.3 2196.75
  5029.9 2198.98  5050.0 2199.93  5110.2 2200.73  5120.2 2199.93  5150.4 2199.94
  5170.4 2201.08  5185.9 2200.89  5230.6 2202.97  5260.8 2203.36  5280.8 2205.15
  5561.8 2213.97  5581.9 2216.31  5602.0 2216.80  5650.7 2220.42  5746.5 2225.67
#Mann=4,-1,0
  4584.7    0.07       0  5007.4    0.05       0  5012.3    0.07       0
  5650.7     0.1       0
Bank Sta=5007.4,5012.3
Exp/Cntr=0.3,0.1

Chan Stop Cuts=-1