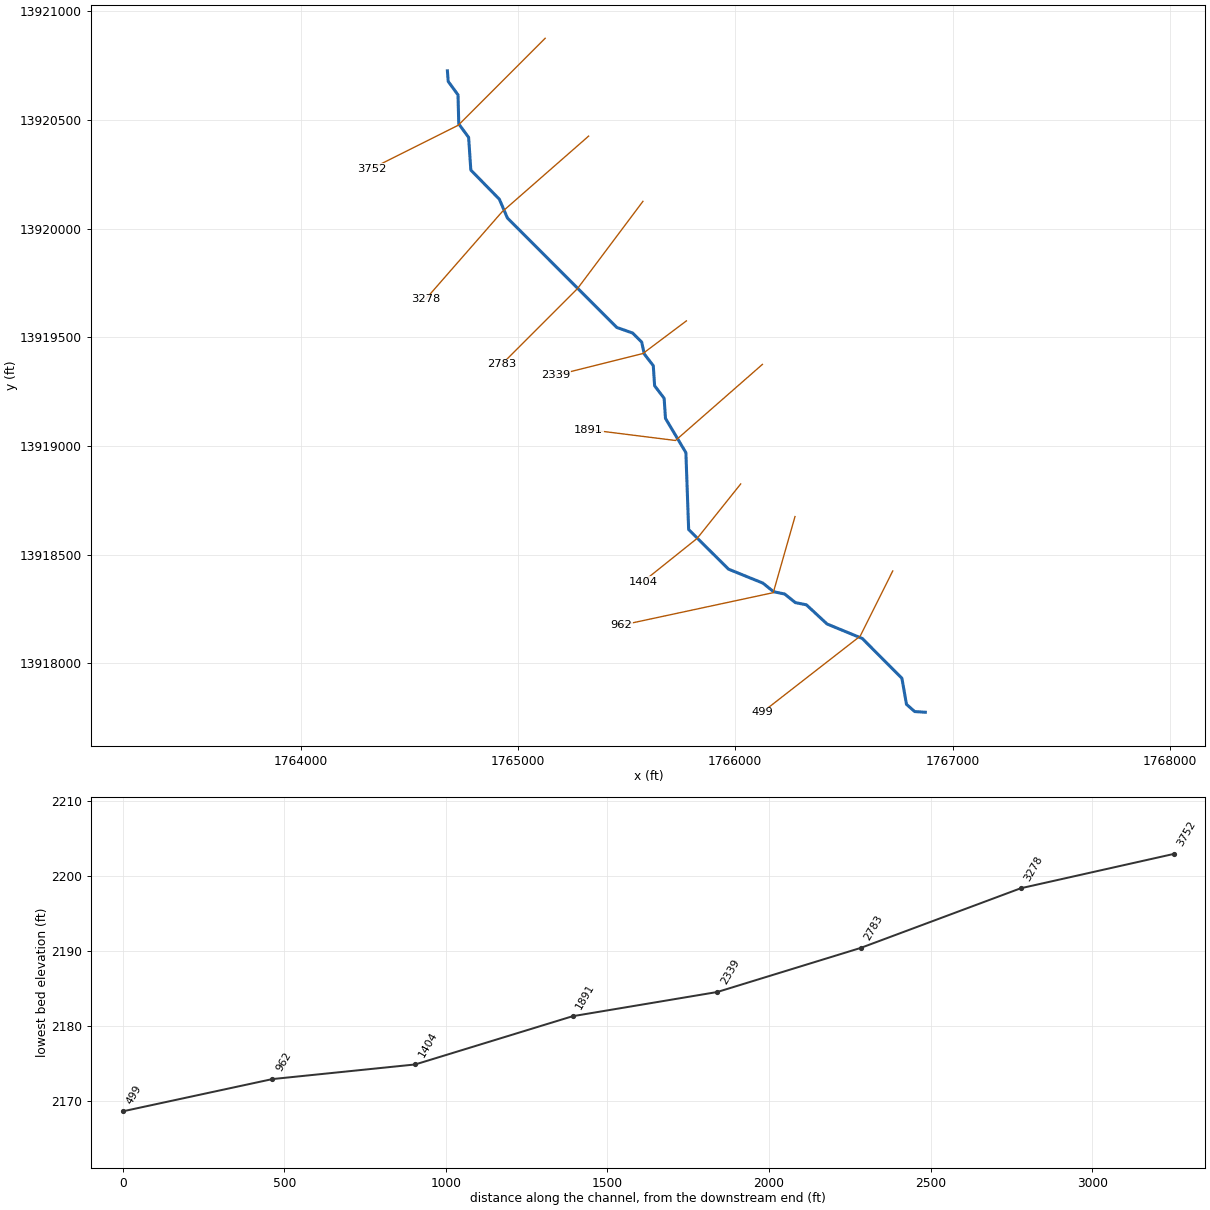
--- Stream0093.prj (project) ---

Proj Title=Stream0093 Base Level Engineering
Current Plan=p01
Default Exp/Contr=0.3,0.1
English Units
Geom File=g01
Flow File=f01
Plan File=p01
BEGIN DESCRIPTION:
Stream0093
END DESCRIPTION:

--- Stream0093.p01 (plan) ---

Plan Title=Multiple Run
Short Identifier=Multiple
Geom File=g01
Flow File=f01
Subcritical Flow
K Sum by GR= 0
Std Step Tol= 0.01
Critical Tol= 0.01
Num of Std Step Trials= 20
Max Error Tol= 0.3
Flow Tol Ratio= 0.001
Split Flow NTrial= 30
Split Flow Tol= 0.02
Split Flow Ratio= 0.02
Log Output Level= 0
Friction Slope Method= 1
Unsteady Friction Slope Method= 2
Unsteady Bridges Friction Slope Method= 1
Parabolic Critical Depth
Global Vel Dist=  1 , 1 , 1
Global Log Level= 0
CheckData=True
Encroach Param= -1, 0, 0, 0
BEGIN DESCRIPTION:
Multiple Run
END DESCRIPTION:

--- Stream0093.f01 (steady flow) ---

Flow Title=Multiple
Number of Profiles=7
Profile Names=10-year,25-year,50-year,1pct_min,100-year,1pct_plu,500-year
River Rch & RM= Stream0093,Reach-1,3752
    1269    2190    3074    2081    4153    8287    7502
Boundary for River Rch & Prof#=Stream0093,Reach-1,1
Up Type=0
Dn Type=3
Dn Slope=0.005
Boundary for River Rch & Prof#=Stream0093,Reach-1,2
Up Type=0
Dn Type=3
Dn Slope=0.005
Boundary for River Rch & Prof#=Stream0093,Reach-1,3
Up Type=0
Dn Type=3
Dn Slope=0.005
Boundary for River Rch & Prof#=Stream0093,Reach-1,4
Up Type=0
Dn Type=3
Dn Slope=0.005
Boundary for River Rch & Prof#=Stream0093,Reach-1,5
Up Type=0
Dn Type=3
Dn Slope=0.005
Boundary for River Rch & Prof#=Stream0093,Reach-1,6
Up Type=0
Dn Type=3
Dn Slope=0.005
Boundary for River Rch & Prof#=Stream0093,Reach-1,7
Up Type=0
Dn Type=3
Dn Slope=0.005

--- Stream0093.g01 (geometry) ---

Geom Title=Existing Conditions

River Reach=Stream0093,Reach-1
Reach XY= 30
      1764675.00     13920725.00      1764678.65     13920676.51
      1764723.87     13920614.53      1764727.27     13920480.94
      1764772.73     13920419.06      1764782.82     13920268.81
      1764914.22     13920134.68      1764951.30     13920048.18
      1765454.92     13919544.79      1765527.54     13919519.25
      1765569.27     13919477.55      1765581.15     13919422.85
      1765622.67     13919369.04      1765628.85     13919276.60
      1765672.65     13919219.03      1765678.83     13919126.58
      1765772.76     13918969.07      1765785.48     13918615.20
      1765968.94     13918433.14      1766127.20     13918368.92
      1766176.72     13918329.16      1766227.20     13918318.92
      1766276.74     13918279.19      1766327.29     13918269.15
      1766422.71     13918180.85      1766584.68     13918114.24
      1766767.14     13917931.17      1766788.12     13917811.35
      1766825.99     13917778.12      1766875.00     13917775.00

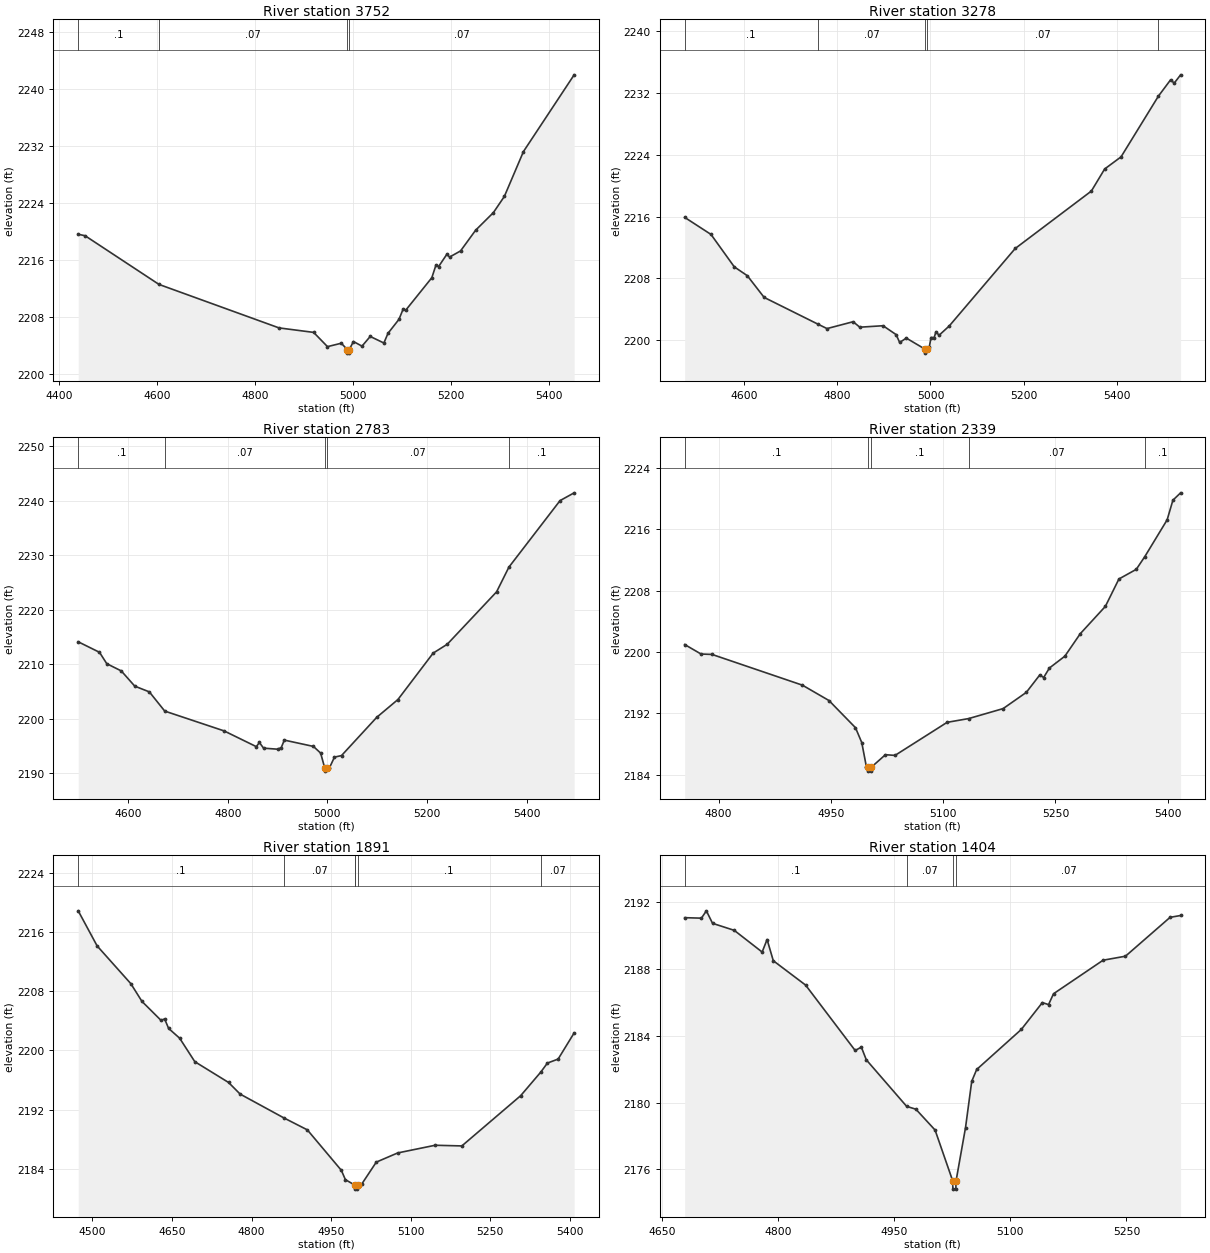
Type RM Length L Ch R = 1,3752,474,474,474
BEGIN DESCRIPTION:
Stream0093 8.0
END DESCRIPTION:
XS GIS Cut Line= 3
      1765124.97     13920874.97      1764725.00     13920475.00
      1764324.97     13920274.98
#Sta/Elev= 30
  4438.9 2219.56  4453.0 2219.35  4603.9 2212.52  4849.0 2206.42  4919.7 2205.79
  4948.0 2203.79  4976.3 2204.27  4988.4 2203.38  4988.6 2202.88  4992.2 2202.88
  4992.5 2203.38  5001.0 2204.51  5018.5 2203.86  5035.3 2205.22  5063.2 2204.30
  5071.6 2205.66  5094.0 2207.62  5102.4 2209.04  5108.0 2208.92  5161.1 2213.46
  5169.5 2215.22  5175.0 2215.03  5191.8 2216.75  5197.4 2216.36  5219.8 2217.22
  5250.5 2220.12  5286.9 2222.60  5309.2 2224.86  5348.3 2231.17  5451.8 2241.93
#Mann=4,-1,0
  4438.9     0.1       0  4603.9    0.07       0  4988.4    0.05       0
  4992.5    0.07       0
Bank Sta=4988.4,4992.5
Exp/Cntr=0.3,0.1

Type RM Length L Ch R = 1,3278,495,495,495
BEGIN DESCRIPTION:
Stream0093 7.0
END DESCRIPTION:
XS GIS Cut Line= 3
      1765324.97     13920424.97      1764925.00     13920075.00
      1764574.98     13919674.98
#Sta/Elev= 30
  4473.2 2215.89  4529.6 2213.68  4579.5 2209.48  4607.5 2208.33  4643.5 2205.52
  4758.3 2202.07  4778.3 2201.48  4834.3 2202.37  4848.5 2201.66  4898.4 2201.85
  4926.4 2200.70  4934.0 2199.68  4948.2 2200.25  4988.8 2198.80  4989.1 2198.30
  4993.0 2198.80  4997.5 2199.11  5001.3 2200.32  5008.0 2200.32  5011.8 2201.08
  5018.4 2200.61  5040.3 2201.82  5181.7 2211.86  5344.9 2219.30  5373.4 2222.16
  5408.5 2223.73  5488.6 2231.60  5514.8 2233.72  5522.4 2233.28  5536.2 2234.36
#Mann=5,-1,0
  4473.2     0.1       0  4758.3    0.07       0  4988.8    0.05       0
  4993.0    0.07       0  5488.6     0.1       0
Bank Sta=4988.8,4993
Exp/Cntr=0.3,0.1

Type RM Length L Ch R = 1,2783,444,444,444
BEGIN DESCRIPTION:
Stream0093 6.0
END DESCRIPTION:
XS GIS Cut Line= 3
      1765574.99     13920124.99      1765275.00     13919725.00
      1764924.97     13919374.97
#Sta/Elev= 30
  4500.0 2214.11  4542.7 2212.18  4557.3 2210.09  4586.4 2208.76  4613.5 2205.96
  4642.7 2204.91  4673.6 2201.38  4792.7 2197.74  4857.3 2194.85  4863.5 2195.61
  4871.9 2194.57  4900.0 2194.38  4907.3 2194.66  4913.5 2196.05  4971.9 2194.89
  4986.4 2193.66  4994.8 2190.85  4995.0 2190.35  4999.0 2190.85  5003.5 2190.85
  5014.1 2192.92  5028.3 2193.21  5099.0 2200.24  5141.4 2203.50  5212.1 2212.03
  5240.4 2213.66  5339.4 2223.29  5364.1 2227.83  5466.7 2240.05  5495.0 2241.48
#Mann=5,-1,0
  4500.0     0.1       0  4673.6    0.07       0  4994.8    0.05       0
  4999.0    0.07       0  5364.1     0.1       0
Bank Sta=4994.8,4999
Exp/Cntr=0.3,0.1

Type RM Length L Ch R = 1,2339,448,448,448
BEGIN DESCRIPTION:
Stream0093 5.0
END DESCRIPTION:
XS GIS Cut Line= 3
      1765775.02     13919575.01      1765575.00     13919425.00
      1765175.03     13919325.01
#Sta/Elev= 30
  4754.8 2200.97  4776.7 2199.73  4791.3 2199.68  4912.1 2195.67  4947.5 2193.67
  4982.9 2190.13  4991.3 2188.19  4997.5 2185.02  4999.5 2184.97  4999.8 2184.47
  5003.6 2184.47  5003.9 2184.97  5022.9 2186.61  5035.7 2186.52  5105.3 2190.83
  5134.1 2191.32  5180.1 2192.62  5211.0 2194.73  5229.0 2197.00  5234.2 2196.67
  5241.9 2197.91  5262.5 2199.45  5283.1 2202.38  5316.6 2205.94  5334.7 2209.51
  5357.9 2210.77  5369.3 2212.43  5399.1 2217.22  5406.8 2219.78  5417.1 2220.74
#Mann=5,-1,0
  4754.8     0.1       0  4999.5    0.05       0  5003.9     0.1       0
  5134.1    0.07       0  5369.3     0.1       0
Bank Sta=4999.5,5003.9
Exp/Cntr=0.3,0.1

Type RM Length L Ch R = 1,1891,487,487,487
BEGIN DESCRIPTION:
Stream0093 4.0
END DESCRIPTION:
XS GIS Cut Line= 3
      1766124.99     13919374.99      1765725.00     13919025.00
      1765325.01     13919075.00
#Sta/Elev= 30
  4473.4 2218.86  4509.0 2214.12  4572.6 2209.01  4593.5 2206.62  4629.5 2204.05
  4636.2 2204.25  4643.8 2202.96  4664.6 2201.64  4693.1 2198.47  4756.7 2195.66
  4778.5 2194.09  4860.4 2190.89  4905.2 2189.25  4969.3 2183.78  4976.9 2182.52
  4995.5 2181.75  4995.6 2181.74  4995.9 2181.24  4999.7 2181.24  5000.0 2181.74
  5007.4 2181.89  5035.1 2184.89  5075.4 2186.13  5146.0 2187.17  5196.4 2187.08
  5307.2 2193.87  5345.0 2197.05  5357.6 2198.28  5377.8 2198.82  5408.0 2202.36
#Mann=6,-1,0
  4473.4     0.1       0  4860.4    0.07       0  4995.5     0.1       0
  4995.6    0.05       0  5000.0     0.1       0  5345.0    0.07       0
Bank Sta=4995.6,5000
Exp/Cntr=0.3,0.1

Type RM Length L Ch R = 1,1404,442,442,442
BEGIN DESCRIPTION:
Stream0093 3.0
END DESCRIPTION:
XS GIS Cut Line= 3
      1766024.99     13918824.99      1765825.00     13918575.00
      1765575.00     13918375.00
#Sta/Elev= 30
  4679.6 2191.08  4701.2 2191.05  4707.6 2191.49  4715.6 2190.74  4743.6 2190.32
  4779.6 2189.02  4786.0 2189.77  4794.0 2188.50  4835.7 2187.04  4899.7 2183.12
  4907.7 2183.32  4914.1 2182.56  4966.2 2179.77  4978.1 2179.60  5002.9 2178.35
  5025.6 2175.31  5025.9 2174.81  5029.7 2174.81  5030.0 2175.31  5042.2 2178.50
  5050.2 2181.27  5056.6 2181.98  5114.2 2184.38  5141.4 2185.99  5149.4 2185.87
  5155.8 2186.52  5219.8 2188.53  5248.7 2188.77  5306.3 2191.10  5319.9 2191.21
#Mann=4,-1,0
  4679.6     0.1       0  4966.2    0.07       0  5025.6    0.05       0
  5030.0    0.07       0
Bank Sta=5025.6,5030
Exp/Cntr=0.3,0.1

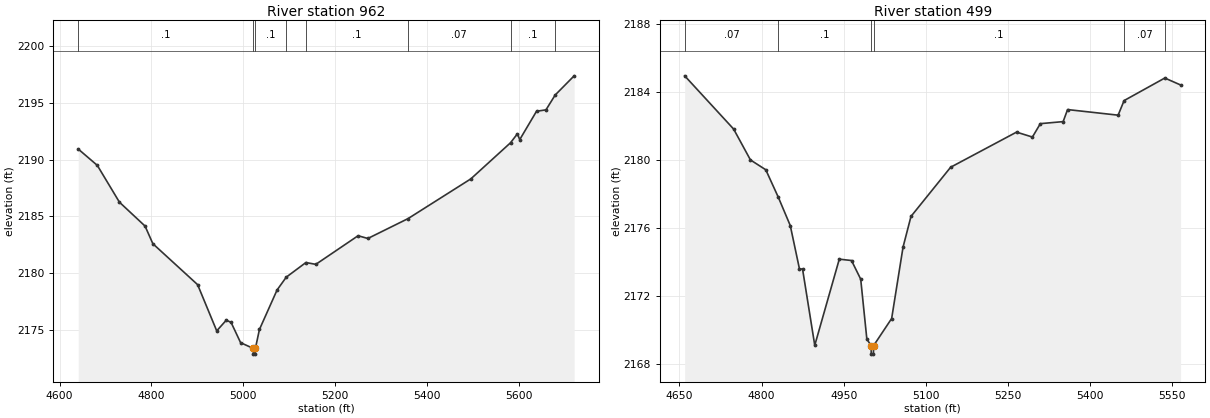
Type RM Length L Ch R = 1,962,463,463,463
BEGIN DESCRIPTION:
Stream0093 2.0
END DESCRIPTION:
XS GIS Cut Line= 3
      1766274.99     13918674.96      1766175.00     13918325.00
      1765474.96     13918174.99
#Sta/Elev= 30
  4640.6 2190.93  4682.2 2189.49  4730.3 2186.25  4786.2 2184.14  4803.1 2182.59
  4900.6 2178.98  4942.2 2174.91  4963.0 2175.85  4973.4 2175.66  4994.2 2173.87
  5021.9 2173.36  5022.2 2172.86  5026.1 2172.86  5026.4 2173.36  5035.2 2175.03
  5073.6 2178.51  5093.6 2179.64  5136.4 2180.93  5158.0 2180.77  5250.0 2183.29
  5271.3 2183.05  5358.8 2184.80  5495.5 2188.30  5581.9 2191.48  5596.9 2192.27
  5602.0 2191.76  5638.6 2194.26  5659.1 2194.38  5679.2 2195.69  5720.5 2197.38
#Mann=8,-1,0
  4640.6     0.1       0  5021.9    0.05       0  5026.4     0.1       0
  5093.6    0.07       0  5136.4     0.1       0  5358.8    0.07       0
  5581.9     0.1       0  5679.2    0.07       0
Bank Sta=5021.9,5026.4
Exp/Cntr=0.3,0.1

Type RM Length L Ch R = 1,499,0,0,0
BEGIN DESCRIPTION:
Stream0093 1.0
END DESCRIPTION:
XS GIS Cut Line= 3
      1766724.98     13918424.96      1766575.00     13918125.00
      1766124.96     13917774.97
#Sta/Elev= 30
  4659.5 2184.97  4748.9 2181.83  4779.6 2180.01  4807.6 2179.43  4830.6 2177.80
  4852.3 2176.14  4869.1 2173.58  4874.7 2173.58  4897.0 2169.08  4941.8 2174.16
  4964.1 2174.08  4980.9 2172.98  4992.1 2169.45  4999.9 2169.06  5000.2 2168.56
  5004.1 2168.56  5004.4 2169.06  5037.4 2170.66  5058.2 2174.87  5072.7 2176.68
  5145.1 2179.58  5265.4 2181.65  5294.4 2181.36  5308.9 2182.15  5350.5 2182.27
  5358.6 2182.98  5450.9 2182.65  5461.8 2183.51  5536.1 2184.84  5565.0 2184.43
#Mann=6,-1,0
  4659.5    0.07       0  4830.6     0.1       0  4999.9    0.05       0
  5004.4     0.1       0  5461.8    0.07       0  5536.1     0.1       0
Bank Sta=4999.9,5004.4
Exp/Cntr=0.3,0.1

Chan Stop Cuts=-1