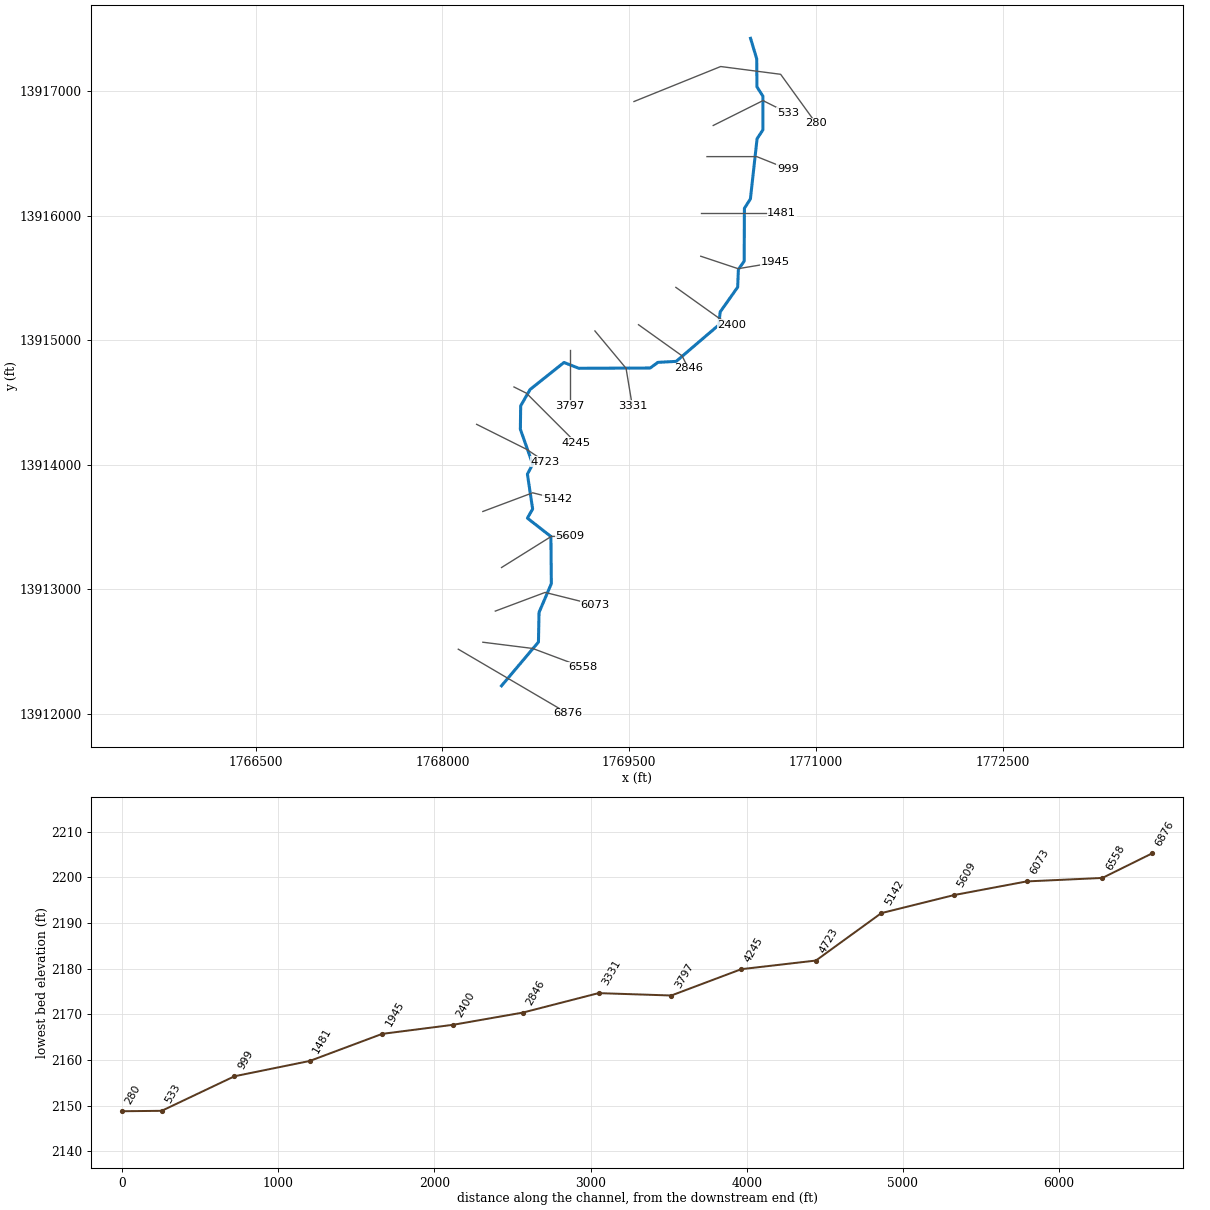
--- Stream0094.prj (project) ---

Proj Title=Stream0094 Base Level Engineering
Current Plan=p01
Default Exp/Contr=0.3,0.1
English Units
Geom File=g01
Flow File=f01
Plan File=p01
BEGIN DESCRIPTION:
Stream0094
END DESCRIPTION:

--- Stream0094.p01 (plan) ---

Plan Title=Multiple Run
Short Identifier=Multiple
Geom File=g01
Flow File=f01
Subcritical Flow
K Sum by GR= 0
Std Step Tol= 0.01
Critical Tol= 0.01
Num of Std Step Trials= 20
Max Error Tol= 0.3
Flow Tol Ratio= 0.001
Split Flow NTrial= 30
Split Flow Tol= 0.02
Split Flow Ratio= 0.02
Log Output Level= 0
Friction Slope Method= 1
Unsteady Friction Slope Method= 2
Unsteady Bridges Friction Slope Method= 1
Parabolic Critical Depth
Global Vel Dist=  1 , 1 , 1
Global Log Level= 0
CheckData=True
Encroach Param= -1, 0, 0, 0
BEGIN DESCRIPTION:
Multiple Run
END DESCRIPTION:

--- Stream0094.f01 (steady flow) ---

Flow Title=Multiple
Number of Profiles=7
Profile Names=10-year,25-year,50-year,1pct_min,100-year,1pct_plu,500-year
River Rch & RM= Stream0094,Reach-1,6876
    1450    2515    3540    2403    4795    9567    8704
Boundary for River Rch & Prof#=Stream0094,Reach-1,1
Up Type=0
Dn Type=3
Dn Slope=0.005
Boundary for River Rch & Prof#=Stream0094,Reach-1,2
Up Type=0
Dn Type=3
Dn Slope=0.005
Boundary for River Rch & Prof#=Stream0094,Reach-1,3
Up Type=0
Dn Type=3
Dn Slope=0.005
Boundary for River Rch & Prof#=Stream0094,Reach-1,4
Up Type=0
Dn Type=3
Dn Slope=0.005
Boundary for River Rch & Prof#=Stream0094,Reach-1,5
Up Type=0
Dn Type=3
Dn Slope=0.005
Boundary for River Rch & Prof#=Stream0094,Reach-1,6
Up Type=0
Dn Type=3
Dn Slope=0.005
Boundary for River Rch & Prof#=Stream0094,Reach-1,7
Up Type=0
Dn Type=3
Dn Slope=0.005

--- Stream0094.g01 (geometry) ---

Geom Title=Existing Conditions

River Reach=Stream0094,Reach-1
Reach XY= 30
      1768475.00     13912225.00      1768771.46     13912576.46
      1768776.22     13912814.50      1768874.93     13913045.03
      1768871.55     13913423.75      1768682.79     13913571.57
      1768724.83     13913644.99      1768682.81     13913924.91
      1768725.21     13914004.79      1768626.22     13914285.51
      1768628.75     13914473.45      1768704.61     13914605.16
      1768976.72     13914821.66      1769095.03     13914775.09
      1769669.06     13914777.26      1769730.94     13914822.73
      1769877.44     13914830.48      1770219.48     13915122.57
      1770230.77     13915227.32      1770371.45     13915426.47
      1770377.27     13915569.06      1770423.78     13915635.50
      1770425.52     13916059.78      1770473.78     13916135.50
      1770527.26     13916619.06      1770574.48     13916690.22
      1770574.48     13916959.78      1770526.22     13917035.50
      1770524.49     13917259.79      1770475.00     13917425.00

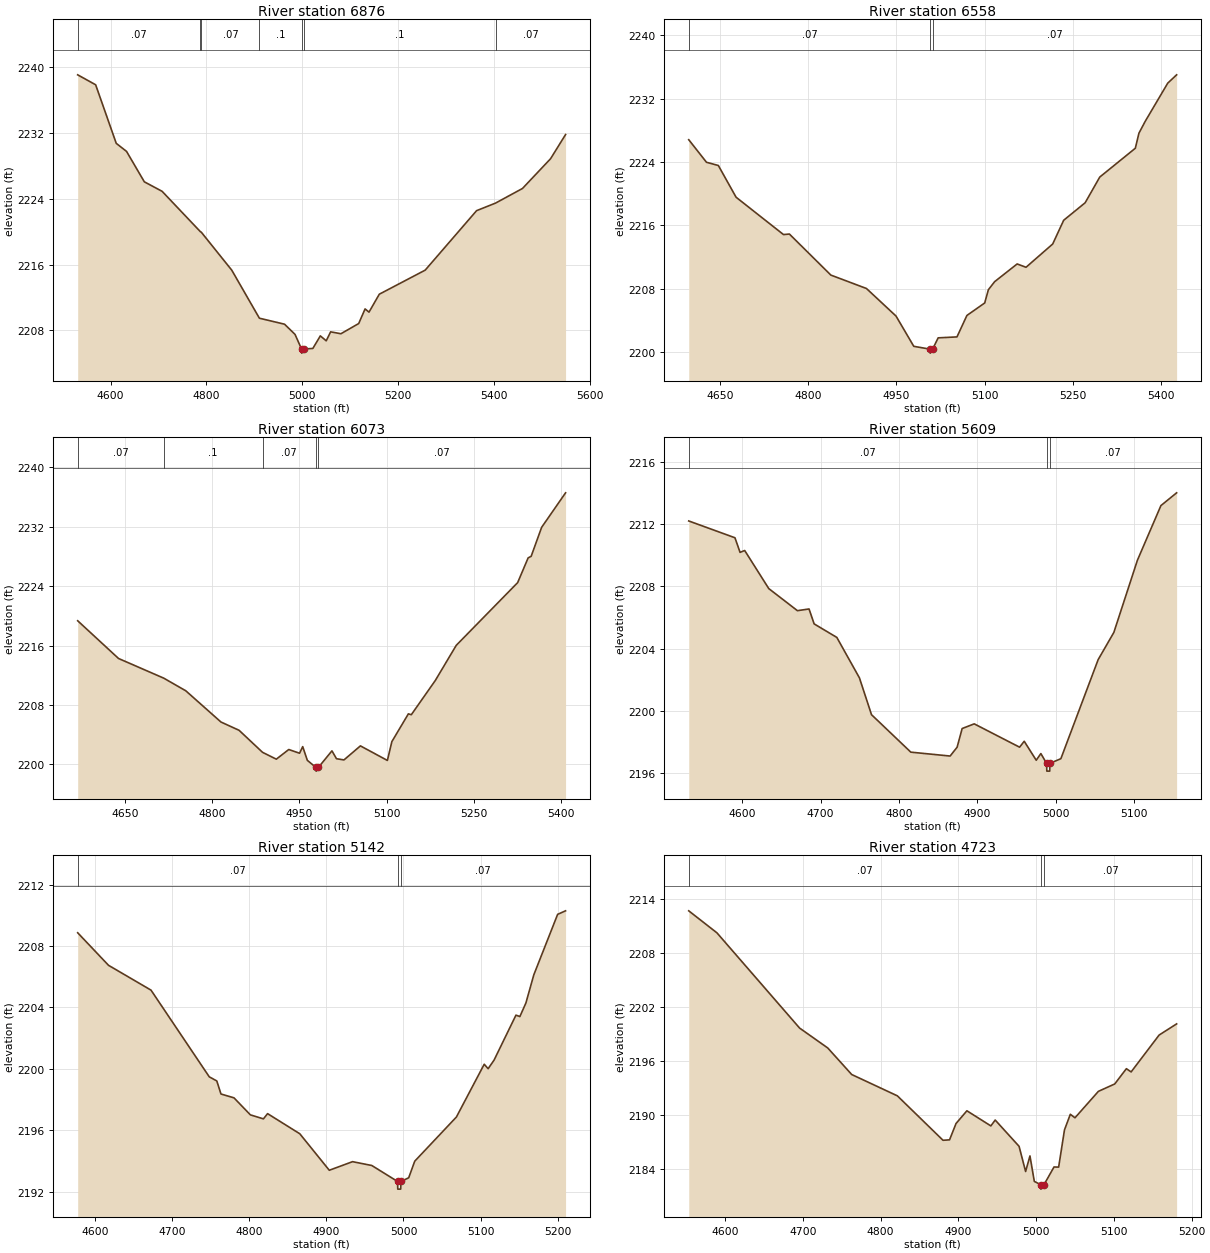
Type RM Length L Ch R = 1,6876,318,318,318
BEGIN DESCRIPTION:
Stream0094 15.0
END DESCRIPTION:
XS GIS Cut Line= 2
      1768127.57     13912518.97      1769005.91     13912003.54
#Sta/Elev= 30
  4531.3 2239.10  4568.8 2237.89  4611.8 2230.76  4633.3 2229.78  4670.4 2226.08
  4707.6 2224.92  4787.6 2220.00  4789.3 2219.95  4853.0 2215.32  4910.6 2209.48
  4963.1 2208.75  4985.0 2207.51  4998.6 2205.73  4998.9 2205.23  5002.7 2205.73
  5022.2 2205.80  5037.8 2207.33  5050.1 2206.73  5059.3 2207.82  5080.8 2207.59
  5117.9 2208.83  5131.2 2210.61  5139.4 2210.22  5160.9 2212.40  5256.7 2215.33
  5364.0 2222.57  5403.6 2223.49  5459.8 2225.27  5518.4 2228.89  5549.7 2231.83
#Mann=7,-1,0
  4531.3    0.07       0  4787.6     0.1       0  4789.3    0.07       0
  4910.6     0.1       0  4998.6    0.05       0  5002.7     0.1       0
  5403.6    0.07       0
Bank Sta=4998.6,5002.7
Exp/Cntr=0.3,0.1

Type RM Length L Ch R = 1,6558,485,485,485
BEGIN DESCRIPTION:
Stream0094 14.0
END DESCRIPTION:
XS GIS Cut Line= 3
      1768324.98     13912575.00      1768725.00     13912525.00
      1769124.97     13912375.01
#Sta/Elev= 30
  4596.6 2226.83  4626.8 2223.98  4647.0 2223.57  4677.2 2219.56  4757.9 2214.84
  4767.9 2214.91  4838.5 2209.72  4899.0 2208.03  4949.3 2204.55  4979.6 2200.72
  5007.5 2200.36  5007.7 2199.86  5011.6 2200.36  5021.1 2201.79  5053.1 2201.91
  5070.0 2204.62  5100.3 2206.20  5106.5 2207.87  5117.2 2208.89  5155.5 2211.13
  5170.6 2210.71  5216.0 2213.65  5234.7 2216.65  5271.2 2218.86  5296.1 2222.11
  5356.6 2225.75  5362.8 2227.66  5373.5 2229.16  5411.8 2233.98  5426.9 2235.03
#Mann=3,-1,0
  4596.6    0.07       0  5007.5    0.05       0  5011.6    0.07       0
Bank Sta=5007.5,5011.6
Exp/Cntr=0.3,0.1

Type RM Length L Ch R = 1,6073,464,464,464
BEGIN DESCRIPTION:
Stream0094 13.0
END DESCRIPTION:
XS GIS Cut Line= 3
      1768424.97     13912824.99      1768825.00     13912975.00
      1769224.96     13912875.01
#Sta/Elev= 30
  4568.5 2219.35  4638.8 2214.27  4716.6 2211.62  4754.5 2209.92  4815.1 2205.71
  4846.2 2204.60  4886.6 2201.63  4910.3 2200.71  4931.7 2202.01  4950.3 2201.51
  4955.7 2202.40  4963.7 2200.55  4978.5 2199.60  4978.8 2199.10  4982.7 2199.60
  5006.0 2201.83  5013.8 2200.77  5026.7 2200.61  5055.0 2202.50  5101.4 2200.54
  5109.1 2203.07  5137.5 2206.81  5142.6 2206.70  5183.9 2211.31  5219.9 2216.04
  5325.6 2224.49  5343.6 2227.82  5348.8 2228.03  5366.8 2231.93  5408.0 2236.58
#Mann=5,-1,0
  4568.5    0.07       0  4716.6     0.1       0  4886.6    0.07       0
  4978.5    0.05       0  4982.7    0.07       0
Bank Sta=4978.5,4982.7
Exp/Cntr=0.3,0.1

Type RM Length L Ch R = 1,5609,467,467,467
BEGIN DESCRIPTION:
Stream0094 12.0
END DESCRIPTION:
XS GIS Cut Line= 3
      1768475.02     13913175.01      1768875.00     13913425.00
      1769025.03     13913425.00
#Sta/Elev= 30
  4532.1 2212.21  4591.0 2211.13  4597.5 2210.19  4603.4 2210.31  4634.1 2207.86
  4670.6 2206.44  4685.4 2206.55  4691.9 2205.59  4720.8 2204.72  4749.6 2202.12
  4765.0 2199.75  4815.1 2197.34  4865.2 2197.09  4874.1 2197.66  4880.5 2198.86
  4895.9 2199.16  4953.7 2197.66  4959.6 2198.04  4974.9 2196.82  4980.8 2197.25
  4988.1 2196.62  4988.4 2196.12  4992.1 2196.12  4992.3 2196.62  5006.3 2196.92
  5053.8 2203.29  5073.8 2205.04  5103.8 2209.68  5133.8 2213.20  5153.8 2214.02
#Mann=3,-1,0
  4532.1    0.07       0  4988.1    0.05       0  4992.3    0.07       0
Bank Sta=4988.1,4992.3
Exp/Cntr=0.3,0.1

Type RM Length L Ch R = 1,5142,419,419,419
BEGIN DESCRIPTION:
Stream0094 11.0
END DESCRIPTION:
XS GIS Cut Line= 3
      1768325.04     13913625.02      1768725.00     13913775.00
      1768924.99     13913725.00
#Sta/Elev= 30
  4577.1 2208.87  4617.1 2206.75  4672.3 2205.13  4747.9 2199.48  4757.7 2199.21
  4763.1 2198.36  4780.0 2198.11  4801.3 2197.00  4818.2 2196.74  4823.6 2197.08
  4865.4 2195.77  4903.7 2193.39  4933.9 2193.95  4958.9 2193.70  4992.3 2192.66
  4992.6 2192.16  4996.4 2192.16  4996.7 2192.66  5006.8 2192.90  5014.6 2193.98
  5068.7 2196.86  5104.8 2200.30  5109.9 2200.01  5117.6 2200.57  5146.0 2203.50
  5151.1 2203.41  5158.9 2204.29  5169.2 2206.13  5200.1 2210.07  5210.4 2210.30
#Mann=3,-1,0
  4577.1    0.07       0  4992.3    0.05       0  4996.7    0.07       0
Bank Sta=4992.3,4996.7
Exp/Cntr=0.3,0.1

Type RM Length L Ch R = 1,4723,478,478,478
BEGIN DESCRIPTION:
Stream0094 10.0
END DESCRIPTION:
XS GIS Cut Line= 3
      1768275.04     13914324.98      1768675.00     13914125.00
      1768824.97     13914025.02
#Sta/Elev= 30
  4553.2 2212.72  4589.5 2210.27  4695.7 2199.69  4732.0 2197.47  4762.8 2194.52
  4821.5 2192.15  4880.2 2187.21  4888.6 2187.26  4896.9 2189.07  4910.9 2190.49
  4941.7 2188.81  4947.3 2189.46  4978.0 2186.54  4986.4 2183.74  4992.0 2185.47
  4997.6 2182.64  5005.7 2182.28  5006.0 2181.78  5010.1 2182.28  5022.9 2184.24
  5028.9 2184.23  5036.4 2188.37  5043.9 2190.10  5049.9 2189.71  5080.0 2192.65
  5101.0 2193.47  5116.0 2195.17  5122.1 2194.81  5158.1 2198.91  5180.6 2200.15
#Mann=3,-1,0
  4553.2    0.07       0  5005.7    0.05       0  5010.1    0.07       0
Bank Sta=5005.7,5010.1
Exp/Cntr=0.3,0.1

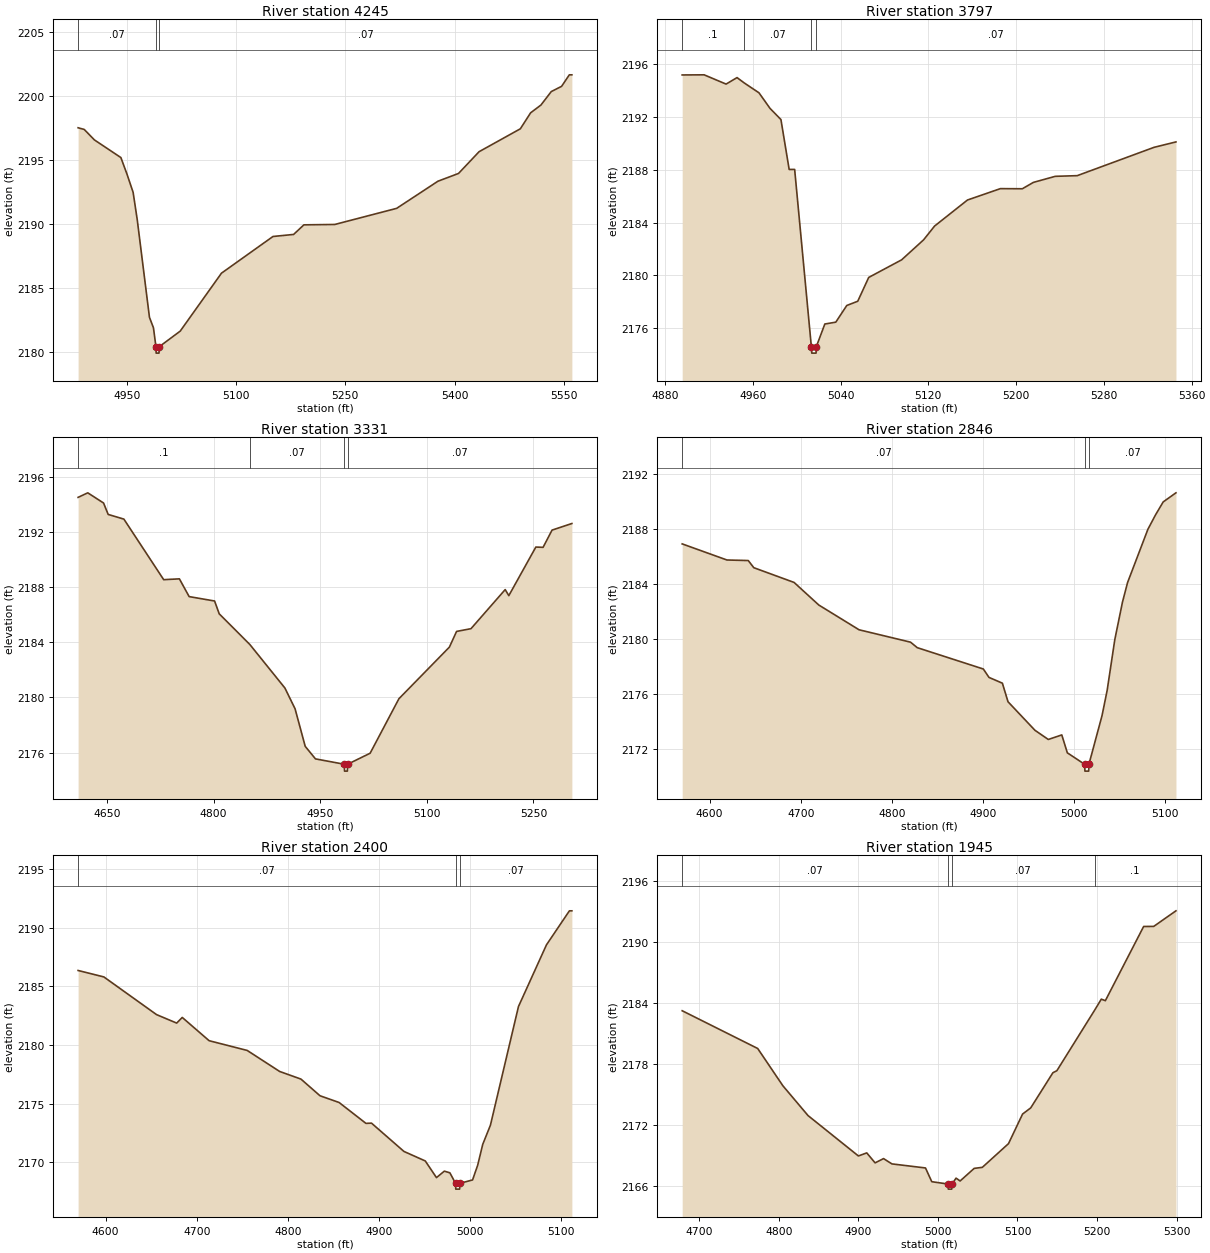
Type RM Length L Ch R = 1,4245,448,448,448
BEGIN DESCRIPTION:
Stream0094 9.0
END DESCRIPTION:
XS GIS Cut Line= 3
      1768574.97     13914625.01      1768675.00     13914575.00
      1769074.99     13914175.01
#Sta/Elev= 30
  4883.4 2197.51  4891.8 2197.38  4905.8 2196.56  4942.1 2195.18  4950.5 2193.88
  4958.9 2192.46  4964.5 2190.34  4981.3 2182.69  4986.8 2181.87  4990.2 2180.39
  4990.5 2179.89  4994.4 2179.89  4994.7 2180.39  5023.5 2181.61  5080.1 2186.14
  5150.8 2189.01  5179.1 2189.17  5193.2 2189.92  5235.6 2189.95  5320.5 2191.21
  5377.1 2193.33  5405.4 2193.94  5433.6 2195.64  5490.2 2197.43  5504.3 2198.68
  5518.5 2199.29  5532.6 2200.34  5546.8 2200.75  5557.4 2201.65  5560.9 2201.65
#Mann=3,-1,0
  4883.4    0.07       0  4990.2    0.05       0  4994.7    0.07       0
Bank Sta=4990.2,4994.7
Exp/Cntr=0.3,0.1

Type RM Length L Ch R = 1,3797,466,466,466
BEGIN DESCRIPTION:
Stream0094 8.0
END DESCRIPTION:
XS GIS Cut Line= 3
      1769025.00     13914925.04      1769025.00     13914825.00
      1769025.00     13914475.04
#Sta/Elev= 30
  4895.7 2195.15  4915.7 2195.16  4935.7 2194.46  4945.7 2194.95  4952.2 2194.55
  4965.7 2193.80  4975.7 2192.63  4985.7 2191.78  4993.2 2188.01  4998.2 2188.01
  5013.4 2174.63  5013.8 2174.13  5017.7 2174.13  5018.0 2174.63  5025.7 2176.33
  5035.7 2176.47  5045.7 2177.73  5055.7 2178.05  5065.7 2179.85  5095.7 2181.18
  5115.7 2182.69  5125.7 2183.73  5155.7 2185.70  5185.7 2186.56  5205.7 2186.55
  5215.7 2187.03  5235.7 2187.49  5255.7 2187.54  5325.7 2189.68  5345.7 2190.09
#Mann=4,-1,0
  4895.7     0.1       0  4952.2    0.07       0  5013.4    0.05       0
  5018.0    0.07       0
Bank Sta=5013.4,5018
Exp/Cntr=0.3,0.1

Type RM Length L Ch R = 1,3331,485,485,485
BEGIN DESCRIPTION:
Stream0094 7.0
END DESCRIPTION:
XS GIS Cut Line= 3
      1769225.02     13915074.98      1769475.00     13914775.00
      1769525.00     13914475.02
#Sta/Elev= 30
  4609.5 2194.54  4623.1 2194.87  4645.3 2194.13  4651.8 2193.30  4673.9 2192.96
  4729.9 2188.56  4752.0 2188.62  4765.7 2187.33  4801.5 2187.01  4808.0 2186.08
  4851.1 2183.85  4900.4 2180.69  4914.7 2179.18  4929.0 2176.45  4943.4 2175.54
  4984.0 2175.15  4984.3 2174.65  4988.3 2174.65  4988.6 2175.15  5020.3 2175.95
  5060.8 2179.91  5131.8 2183.66  5141.9 2184.80  5162.2 2185.00  5210.3 2187.84
  5215.4 2187.40  5253.4 2190.93  5263.6 2190.91  5276.2 2192.16  5304.1 2192.64
#Mann=4,-1,0
  4609.5     0.1       0  4851.1    0.07       0  4984.0    0.05       0
  4988.6    0.07       0
Bank Sta=4984,4988.6
Exp/Cntr=0.3,0.1

Type RM Length L Ch R = 1,2846,446,446,446
BEGIN DESCRIPTION:
Stream0094 6.0
END DESCRIPTION:
XS GIS Cut Line= 3
      1769575.04     13915124.97      1769925.00     13914875.00
      1769975.01     13914774.98
#Sta/Elev= 30
  4569.9 2186.90  4619.0 2185.73  4642.4 2185.69  4648.5 2185.17  4692.7 2184.10
  4719.8 2182.46  4764.0 2180.66  4820.5 2179.76  4827.9 2179.36  4900.4 2177.81
  4906.6 2177.20  4921.3 2176.78  4927.5 2175.43  4957.0 2173.36  4971.7 2172.69
  4986.5 2173.02  4992.6 2171.72  5011.5 2170.89  5011.9 2170.39  5016.0 2170.39
  5016.3 2170.89  5030.7 2174.43  5036.3 2176.26  5044.7 2179.95  5053.1 2182.67
  5058.7 2184.09  5081.0 2187.96  5089.4 2189.01  5097.8 2189.95  5111.8 2190.61
#Mann=3,-1,0
  4569.9    0.07       0  5011.5    0.05       0  5016.3    0.07       0
Bank Sta=5011.5,5016.3
Exp/Cntr=0.3,0.1

Type RM Length L Ch R = 1,2400,455,455,455
BEGIN DESCRIPTION:
Stream0094 5.0
END DESCRIPTION:
XS GIS Cut Line= 3
      1769874.98     13915425.02      1770225.00     13915175.00
      1770324.96     13915125.02
#Sta/Elev= 30
  4569.8 2186.34  4598.1 2185.79  4655.9 2182.58  4678.0 2181.86  4684.1 2182.34
  4713.6 2180.36  4755.4 2179.53  4791.0 2177.74  4814.4 2177.09  4835.3 2175.67
  4856.2 2175.10  4885.7 2173.32  4891.8 2173.34  4927.4 2170.93  4950.8 2170.12
  4963.1 2168.70  4971.7 2169.25  4977.8 2169.11  4984.0 2168.22  4984.3 2167.72
  4988.5 2167.72  4988.9 2168.22  5002.7 2168.50  5008.3 2169.75  5013.9 2171.54
  5022.3 2173.16  5053.1 2183.27  5083.8 2188.52  5109.0 2191.42  5111.7 2191.42
#Mann=3,-1,0
  4569.8    0.07       0  4984.0    0.05       0  4988.9    0.07       0
Bank Sta=4984,4988.9
Exp/Cntr=0.3,0.1

Type RM Length L Ch R = 1,1945,464,464,464
BEGIN DESCRIPTION:
Stream0094 4.0
END DESCRIPTION:
XS GIS Cut Line= 3
      1770075.00     13915675.00      1770375.00     13915575.00
      1770675.03     13915625.00
#Sta/Elev= 30
  4678.7 2183.26  4773.6 2179.55  4805.2 2175.89  4836.8 2172.96  4900.1 2168.99
  4910.6 2169.29  4921.1 2168.31  4931.7 2168.73  4942.2 2168.21  4984.4 2167.81
  4992.3 2166.46  5012.7 2166.23  5013.1 2165.73  5017.4 2165.73  5017.8 2166.23
  5022.8 2166.81  5027.9 2166.53  5045.6 2167.77  5055.8 2167.87  5088.7 2170.20
  5106.4 2173.11  5116.6 2173.71  5144.5 2177.17  5149.5 2177.37  5196.8 2183.30
  5205.3 2184.40  5210.4 2184.25  5258.5 2191.54  5271.2 2191.55  5299.1 2193.08
#Mann=4,-1,0
  4678.7    0.07       0  5012.7    0.05       0  5017.8    0.07       0
  5196.8     0.1       0
Bank Sta=5012.7,5017.8
Exp/Cntr=0.3,0.1

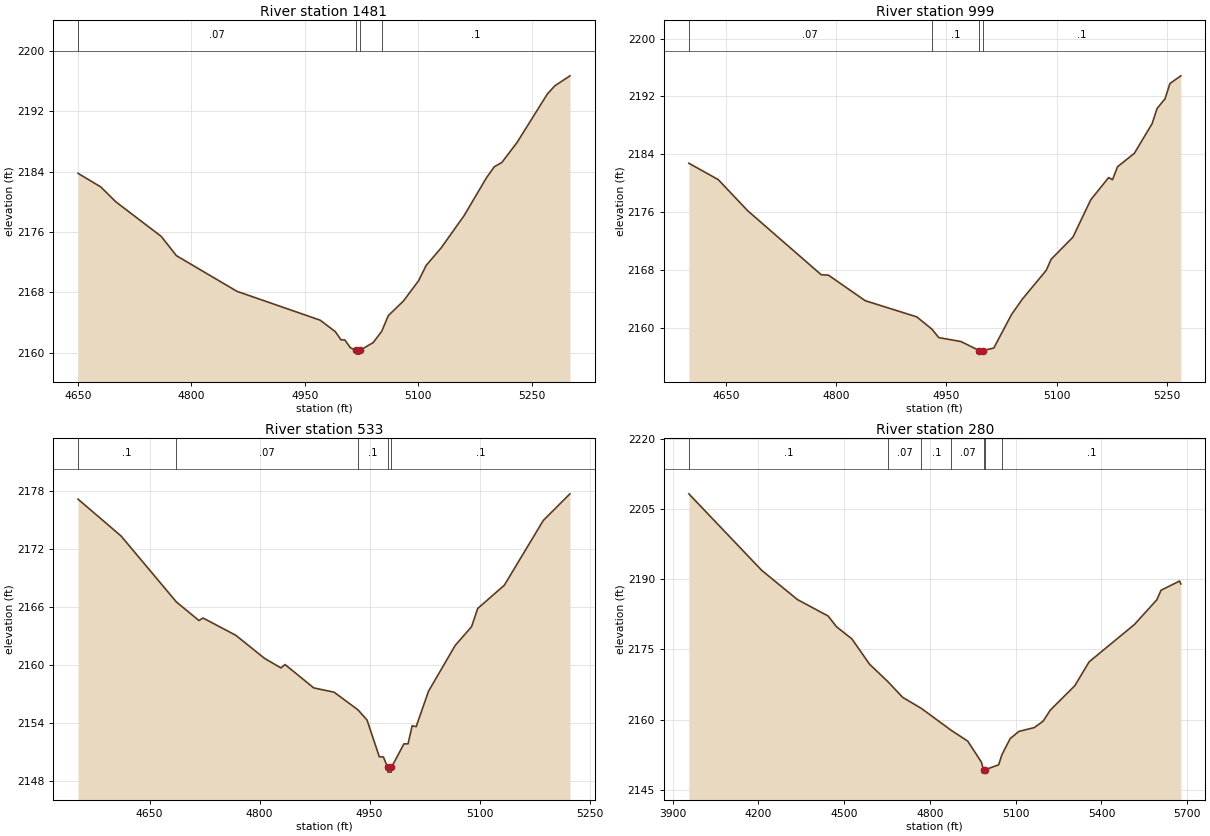
Type RM Length L Ch R = 1,1481,482,482,482
BEGIN DESCRIPTION:
Stream0094 3.0
END DESCRIPTION:
XS GIS Cut Line= 3
      1770075.02     13916025.00      1770425.00     13916025.00
      1770725.02     13916025.00
#Sta/Elev= 30
  4650.4 2183.78  4680.4 2181.98  4700.4 2180.00  4760.4 2175.41  4780.4 2172.86
  4860.4 2168.13  4970.4 2164.30  4990.4 2162.78  4997.9 2161.69  5002.9 2161.69
  5010.4 2160.63  5017.8 2160.30  5018.2 2159.80  5022.5 2159.80  5022.9 2160.30
  5040.4 2161.33  5051.7 2162.83  5060.4 2164.91  5080.4 2166.85  5100.4 2169.54
  5110.4 2171.56  5130.4 2173.92  5160.4 2178.15  5190.4 2183.24  5200.4 2184.65
  5210.4 2185.22  5230.4 2187.86  5270.4 2194.28  5280.4 2195.39  5300.4 2196.71
#Mann=4,-1,0
  4650.4    0.07       0  5017.8    0.05       0  5022.9    0.07       0
  5051.7     0.1       0
Bank Sta=5017.8,5022.9
Exp/Cntr=0.3,0.1

Type RM Length L Ch R = 1,999,466,466,466
BEGIN DESCRIPTION:
Stream0094 2.0
END DESCRIPTION:
XS GIS Cut Line= 3
      1770125.02     13916475.00      1770525.00     13916475.00
      1770774.97     13916375.01
#Sta/Elev= 30
  4599.6 2182.79  4639.6 2180.53  4679.6 2176.24  4779.6 2167.41  4789.6 2167.34
  4839.6 2163.82  4909.6 2161.59  4930.0 2159.92  4939.6 2158.73  4969.6 2158.19
  4994.5 2156.95  4994.9 2156.45  4999.3 2156.45  4999.7 2156.95  5014.4 2157.29
  5038.6 2161.93  5053.4 2164.06  5085.7 2168.01  5092.5 2169.55  5122.1 2172.60
  5146.3 2177.75  5170.6 2180.81  5175.9 2180.52  5182.7 2182.30  5205.6 2184.16
  5229.8 2188.26  5236.5 2190.34  5247.3 2191.68  5254.0 2193.79  5268.8 2194.85
#Mann=4,-1,0
  4599.6    0.07       0  4930.0     0.1       0  4994.5    0.05       0
  4999.7     0.1       0
Bank Sta=4994.5,4999.7
Exp/Cntr=0.3,0.1

Type RM Length L Ch R = 1,533,253,253,253
BEGIN DESCRIPTION:
Stream0094 1.0
END DESCRIPTION:
XS GIS Cut Line= 3
      1770175.04     13916725.02      1770575.00     13916925.00
      1770775.02     13916824.99
#Sta/Elev= 30
  4552.4 2177.18  4611.1 2173.36  4686.6 2166.52  4717.3 2164.60  4722.9 2164.86
  4767.6 2163.07  4806.7 2160.68  4829.1 2159.69  4834.7 2160.04  4873.8 2157.62
  4901.7 2157.17  4934.2 2155.34  4946.5 2154.29  4963.2 2150.49  4968.8 2150.46
  4974.6 2149.39  4975.0 2148.89  4979.4 2148.89  4979.8 2149.39  4996.8 2151.82
  5002.4 2151.82  5008.0 2153.69  5013.5 2153.61  5030.3 2157.27  5066.7 2162.02
  5089.0 2163.96  5097.4 2165.85  5133.7 2168.26  5186.8 2174.97  5223.2 2177.73
#Mann=5,-1,0
  4552.4     0.1       0  4686.6    0.07       0  4934.2     0.1       0
  4974.6    0.05       0  4979.8     0.1       0
Bank Sta=4974.6,4979.8
Exp/Cntr=0.3,0.1

Type RM Length L Ch R = 1,280,0,0,0
BEGIN DESCRIPTION:
Stream0094 0.0
END DESCRIPTION:
XS GIS Cut Line= 4
      1769538.68     13916917.44      1770235.08     13917198.61
      1770716.56     13917136.17      1771000.21     13916743.54
#Sta/Elev= 30
  3956.6 2208.23  4211.5 2191.89  4336.4 2185.65  4443.8 2182.14  4473.3 2179.83
  4527.0 2177.25  4588.9 2171.83  4652.4 2168.15  4704.9 2164.75  4769.2 2162.44
  4875.0 2157.70  4932.2 2155.42  4979.8 2150.95  4987.3 2149.30  4987.7 2148.80
  4992.5 2149.30  5040.3 2150.37  5051.6 2152.51  5080.6 2155.96  5110.9 2157.49
  5164.8 2158.31  5196.1 2159.69  5220.7 2162.03  5306.6 2167.25  5356.9 2172.36
  5515.3 2180.33  5593.6 2185.61  5608.3 2187.64  5673.3 2189.61  5677.5 2188.99
#Mann=7,-1,0
  3956.6     0.1       0  4652.4    0.07       0  4769.2     0.1       0
  4875.0    0.07       0  4987.3    0.05       0  4992.5    0.07       0
  5051.6     0.1       0
Bank Sta=4987.3,4992.5
Exp/Cntr=0.3,0.1

Chan Stop Cuts=-1