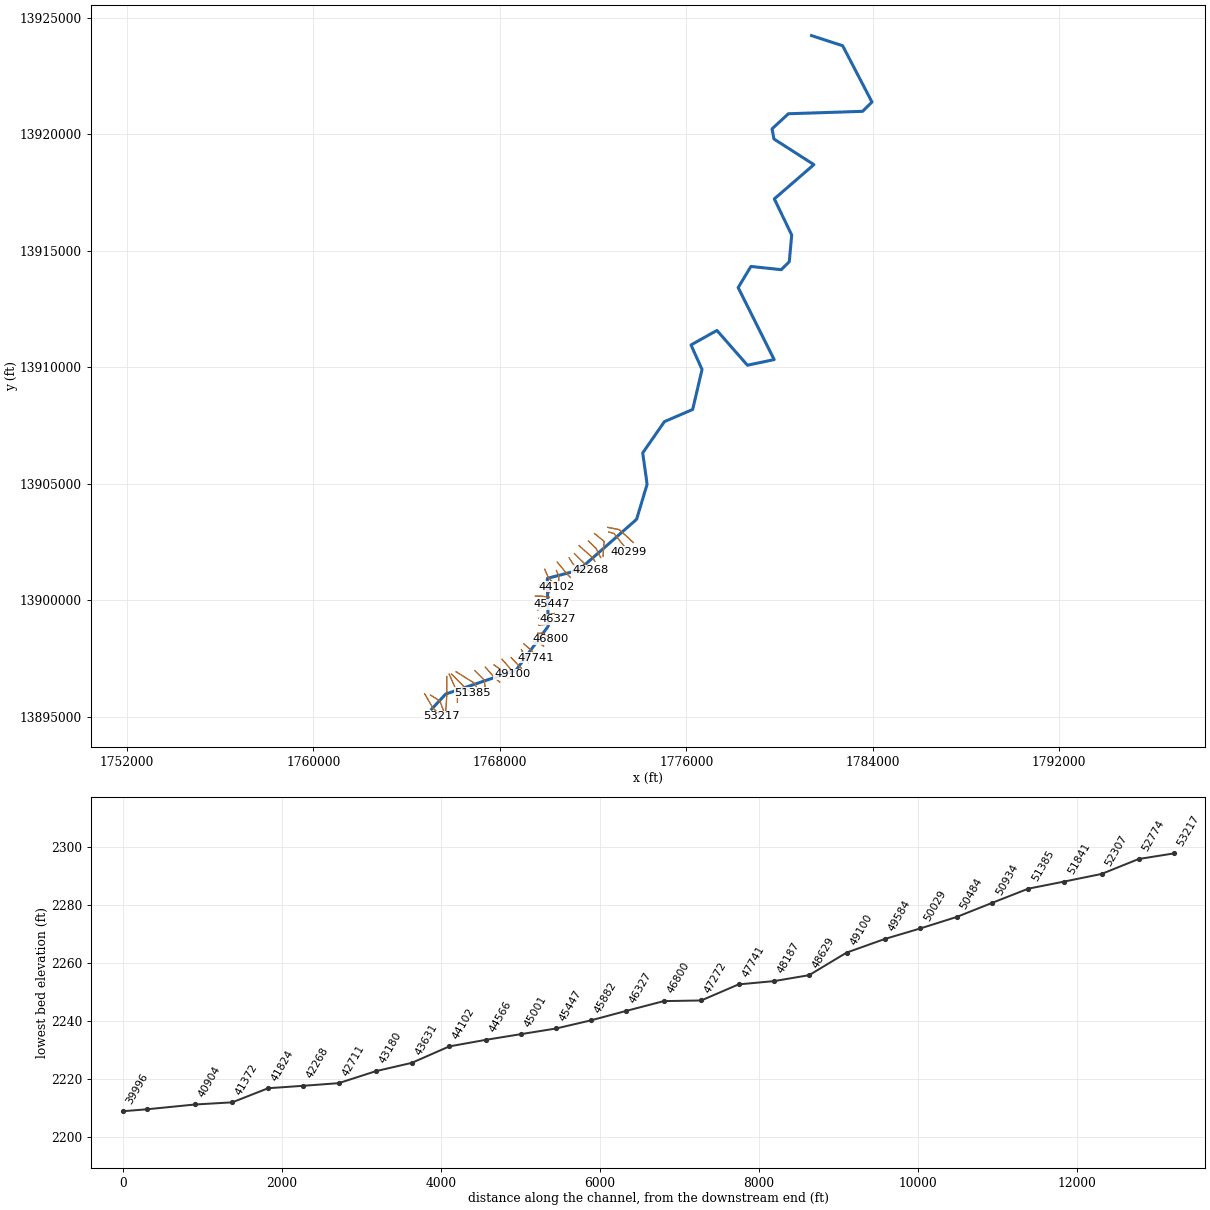
--- Stream0095.prj (project) ---

Proj Title=Stream0095 Base Level Engineering
Current Plan=p01
Default Exp/Contr=0.3,0.1
English Units
Geom File=g01
Flow File=f01
Plan File=p01
BEGIN DESCRIPTION:
Stream0095
END DESCRIPTION:

--- Stream0095.p01 (plan) ---

Plan Title=Multiple Run
Short Identifier=Multiple
Geom File=g01
Flow File=f01
Subcritical Flow
K Sum by GR= 0
Std Step Tol= 0.01
Critical Tol= 0.01
Num of Std Step Trials= 20
Max Error Tol= 0.3
Flow Tol Ratio= 0.001
Split Flow NTrial= 30
Split Flow Tol= 0.02
Split Flow Ratio= 0.02
Log Output Level= 0
Friction Slope Method= 1
Unsteady Friction Slope Method= 2
Unsteady Bridges Friction Slope Method= 1
Parabolic Critical Depth
Global Vel Dist=  1 , 1 , 1
Global Log Level= 0
CheckData=True
Encroach Param= -1, 0, 0, 0
BEGIN DESCRIPTION:
Multiple Run
END DESCRIPTION:

--- Stream0095.f01 (steady flow) ---

Flow Title=Multiple
Number of Profiles=7
Profile Names=10-year,25-year,50-year,1pct_min,100-year,1pct_plu,500-year
River Rch & RM= Stream0095,Reach-1,53217
    1767    3070    4327    2938    5862   11696   10649
River Rch & RM= Stream0095,Reach-1,46327
    1845    3207    4522    3070    6126   12223   11132
River Rch & RM= Stream0095,Reach-1,44102
    2374    4181    5945    4069    8119   16200   14993
River Rch & RM= Stream0095,Reach-1,43631
    2447    4310    6129    4195    8371   16701   15457
River Rch & RM= Stream0095,Reach-1,40299
    3894    6993   10078    6979   13924   27783   26325
River Rch & RM= Stream0095,Reach-1,36335
    4673    8439   12205    8478   16916   33751   32177
River Rch & RM= Stream0095,Reach-1,32233
    4475    8070   11657    8084   16129   32182   30597
River Rch & RM= Stream0095,Reach-1,24258
    5165    9339   13513    9380   18716   37342   35560
River Rch & RM= Stream0095,Reach-1,13388
    5349    9672   13994    9712   19378   38664   36805
River Rch & RM= Stream0095,Reach-1,7229
    5317    9605   13887    9631   19216   38341   36443
River Rch & RM= Stream0095,Reach-1,4937
    5493    9932   14370    9971   19895   39697   37773
Boundary for River Rch & Prof#=Stream0095,Reach-1,1
Up Type=0
Dn Type=3
Dn Slope=0.005
Boundary for River Rch & Prof#=Stream0095,Reach-1,2
Up Type=0
Dn Type=3
Dn Slope=0.005
Boundary for River Rch & Prof#=Stream0095,Reach-1,3
Up Type=0
Dn Type=3
Dn Slope=0.005
Boundary for River Rch & Prof#=Stream0095,Reach-1,4
Up Type=0
Dn Type=3
Dn Slope=0.005
Boundary for River Rch & Prof#=Stream0095,Reach-1,5
Up Type=0
Dn Type=3
Dn Slope=0.005
Boundary for River Rch & Prof#=Stream0095,Reach-1,6
Up Type=0
Dn Type=3
Dn Slope=0.005
Boundary for River Rch & Prof#=Stream0095,Reach-1,7
Up Type=0
Dn Type=3
Dn Slope=0.005

--- Stream0095.g01 (geometry) ---

Geom Title=Existing Conditions

River Reach=Stream0095,Reach-1
Reach XY= 30
      1765075.00     13895325.00      1765676.45     13895971.47
      1768692.13     13896991.25      1770073.04     13898880.89
      1770035.70     13900934.71      1771381.05     13901283.16
      1773866.98     13903468.66      1774317.44     13904975.00
      1774128.50     13906316.52      1775061.76     13907661.38
      1776272.75     13908180.93      1776675.49     13909899.96
      1776201.17     13910951.87      1777314.50     13911573.78
      1778622.70     13910080.83      1779769.94     13910322.71
      1778226.10     13913414.45      1778772.57     13914319.48
      1780074.95     13914182.28      1780419.48     13914522.57
      1780522.74     13915669.06      1779777.14     13917219.03
      1781475.43     13918690.18      1779761.76     13919788.61
      1779678.75     13920223.45      1780380.94     13920872.73
      1783563.05     13920975.84      1783967.67     13921374.90
      1782708.51     13923792.05      1781375.00     13924225.00

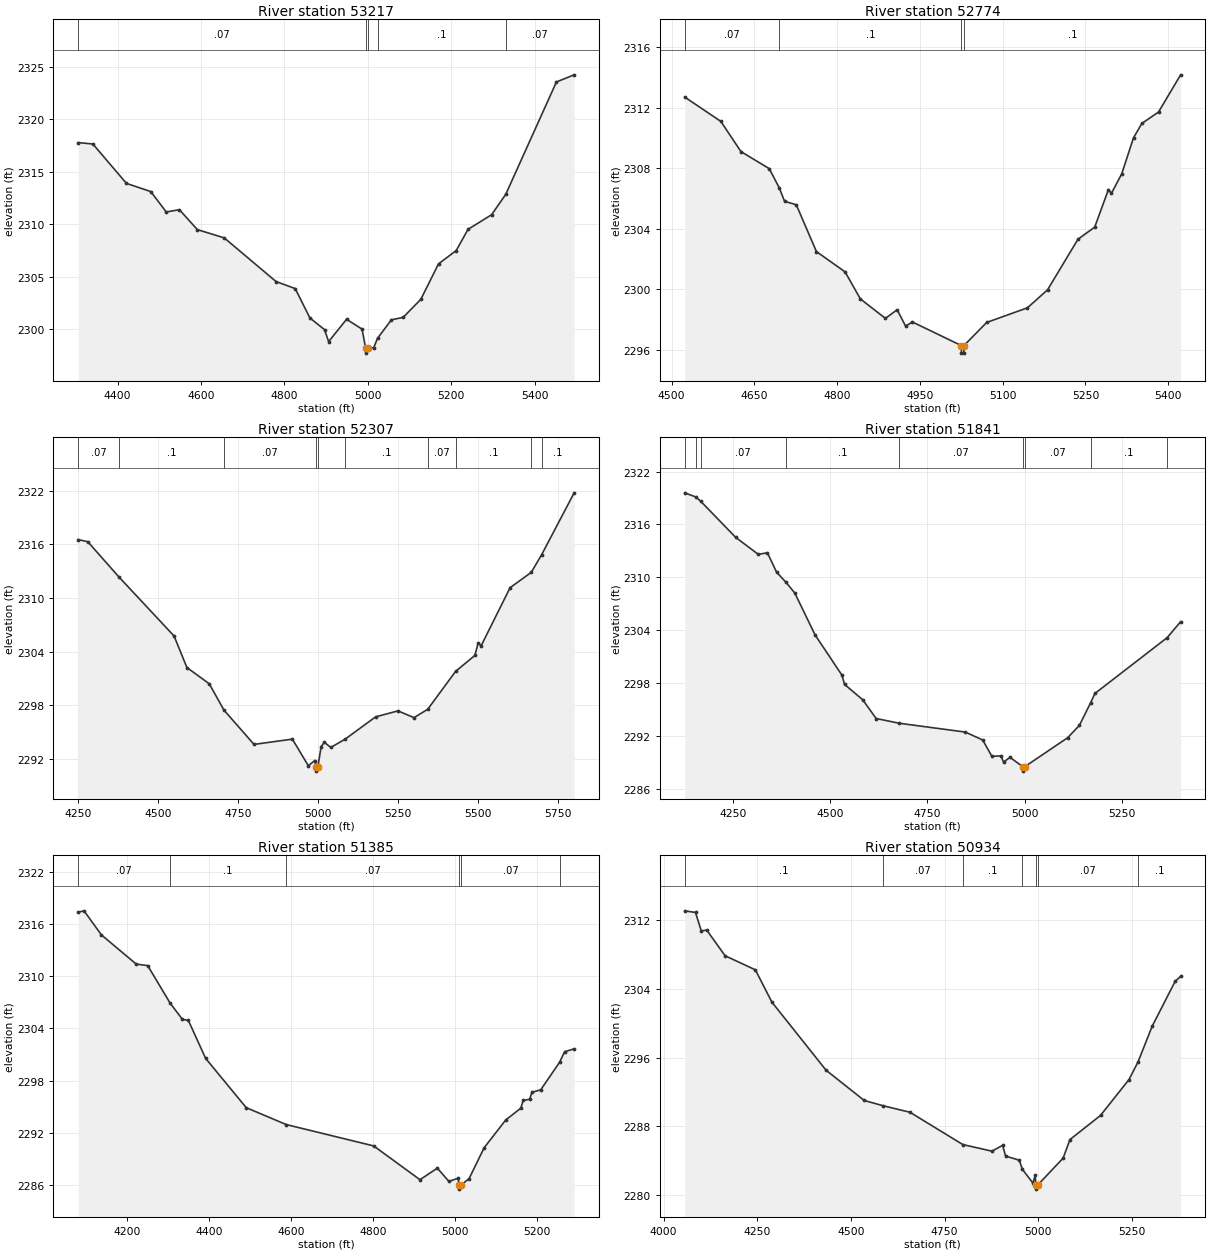
Type RM Length L Ch R = 1,53217,443,443,443
BEGIN DESCRIPTION:
Stream0095 102.0
END DESCRIPTION:
XS GIS Cut Line= 3
      1764775.02     13895974.97      1765125.00     13895375.00
      1765475.03     13895024.97
#Sta/Elev= 30
  4305.4 2317.78  4340.5 2317.65  4421.1 2313.89  4479.4 2313.11  4516.6 2311.16
  4548.1 2311.38  4591.1 2309.48  4655.6 2308.69  4780.0 2304.52  4825.9 2303.85
  4861.1 2301.05  4896.2 2299.93  4906.1 2298.79  4949.1 2300.92  4986.3 2299.98
  4994.7 2298.19  4995.1 2297.69  4999.4 2298.19  5014.1 2298.19  5023.3 2299.10
  5056.6 2300.87  5084.8 2301.10  5127.3 2302.83  5169.7 2306.21  5212.1 2307.48
  5240.4 2309.50  5297.0 2310.90  5331.0 2312.85  5452.5 2323.57  5495.0 2324.25
#Mann=5,-1,0
  4305.4    0.07       0  4994.7    0.05       0  4999.4    0.07       0
  5023.3     0.1       0  5331.0    0.07       0
Bank Sta=4994.7,4999.4
Exp/Cntr=0.3,0.1

Type RM Length L Ch R = 1,52774,467,467,467
BEGIN DESCRIPTION:
Stream0095 101.0
END DESCRIPTION:
XS GIS Cut Line= 3
      1765024.97     13895925.02      1765425.00     13895675.00
      1765574.99     13895275.03
#Sta/Elev= 30
  4523.7 2312.71  4589.2 2311.10  4625.7 2309.10  4677.0 2307.97  4695.4 2306.68
  4704.7 2305.81  4726.0 2305.58  4762.5 2302.48  4814.4 2301.14  4842.1 2299.35
  4887.5 2298.06  4908.8 2298.63  4924.1 2297.55  4936.5 2297.82  5025.1 2296.26
  5025.4 2295.76  5029.5 2295.76  5029.9 2296.26  5071.1 2297.79  5145.0 2298.76
  5181.4 2299.95  5236.6 2303.30  5266.9 2304.10  5291.8 2306.59  5297.1 2306.33
  5315.8 2307.62  5337.2 2310.01  5352.3 2310.96  5382.6 2311.72  5422.6 2314.18
#Mann=4,-1,0
  4523.7    0.07       0  4695.4     0.1       0  5025.1    0.05       0
  5029.9     0.1       0
Bank Sta=5025.1,5029.9
Exp/Cntr=0.3,0.1

Type RM Length L Ch R = 1,52307,466,466,466
BEGIN DESCRIPTION:
Stream0095 100.0
END DESCRIPTION:
XS GIS Cut Line= 3
      1765725.00     13896725.02      1765725.00     13895975.00
      1765675.00     13895174.98
#Sta/Elev= 30
  4250.4 2316.52  4280.4 2316.28  4376.7 2312.38  4550.4 2305.73  4590.4 2302.21
  4660.4 2300.39  4706.5 2297.44  4800.4 2293.61  4920.4 2294.20  4970.4 2291.22
  4990.4 2291.80  4995.5 2291.12  4995.9 2290.62  5000.3 2291.12  5010.4 2293.37
  5020.5 2293.85  5040.5 2293.27  5085.3 2294.19  5180.8 2296.69  5250.9 2297.36
  5301.0 2296.60  5343.9 2297.54  5431.1 2301.78  5491.4 2303.56  5501.4 2304.91
  5511.4 2304.67  5601.6 2311.14  5667.7 2312.85  5700.0 2314.81  5802.0 2321.75
#Mann=10,-1,0
  4250.4    0.07       0  4376.7     0.1       0  4706.5    0.07       0
  4995.5    0.05       0  5000.3    0.07       0  5085.3     0.1       0
  5343.9    0.07       0  5431.1     0.1       0  5667.7    0.07       0
  5700.0     0.1       0
Bank Sta=4995.5,5000.3
Exp/Cntr=0.3,0.1

Type RM Length L Ch R = 1,51841,456,456,456
BEGIN DESCRIPTION:
Stream0095 99.0
END DESCRIPTION:
XS GIS Cut Line= 3
      1765825.02     13896824.96      1766175.00     13896025.00
      1766175.00     13895624.97
#Sta/Elev= 30
  4126.8 2319.59  4155.4 2319.12  4167.6 2318.65  4257.7 2314.54  4315.8 2312.61
  4339.2 2312.79  4362.6 2310.60  4386.7 2309.45  4409.4 2308.23  4461.6 2303.47
  4530.6 2298.90  4537.2 2297.86  4584.0 2296.11  4618.3 2293.99  4677.8 2293.45
  4847.2 2292.45  4892.0 2291.55  4915.4 2289.70  4938.8 2289.75  4945.4 2289.05
  4962.2 2289.58  4994.7 2288.52  4995.1 2288.02  4999.8 2288.52  5110.0 2291.81
  5140.0 2293.20  5168.7 2295.75  5180.0 2296.83  5365.4 2303.16  5400.0 2304.97
#Mann=9,-1,0
  4126.8    0.07       0  4155.4     0.1       0  4167.6    0.07       0
  4386.7     0.1       0  4677.8    0.07       0  4994.7    0.05       0
  4999.8    0.07       0  5168.7     0.1       0  5365.4    0.07       0
Bank Sta=4994.7,4999.8
Exp/Cntr=0.3,0.1

Type RM Length L Ch R = 1,51385,451,451,451
BEGIN DESCRIPTION:
Stream0095 98.0
END DESCRIPTION:
XS GIS Cut Line= 3
      1765924.97     13896825.03      1766575.00     13896175.00
      1766824.98     13896025.01
#Sta/Elev= 30
  4080.7 2317.33  4094.9 2317.49  4137.3 2314.73  4222.2 2311.38  4250.4 2311.20
  4304.8 2306.92  4335.3 2305.02  4349.4 2304.93  4391.9 2300.55  4490.9 2294.90
  4588.6 2292.96  4802.0 2290.51  4915.1 2286.63  4957.5 2287.96  4985.8 2286.43
  5007.8 2286.80  5010.9 2286.05  5011.3 2285.55  5016.3 2286.05  5035.0 2286.76
  5071.9 2290.31  5124.4 2293.48  5161.3 2294.84  5167.1 2295.73  5182.7 2295.86
  5188.5 2296.66  5209.9 2296.95  5255.8 2300.10  5268.2 2301.32  5291.5 2301.65
#Mann=6,-1,0
  4080.7    0.07       0  4304.8     0.1       0  4588.6    0.07       0
  5010.9    0.05       0  5016.3    0.07       0  5255.8     0.1       0
Bank Sta=5010.9,5016.3
Exp/Cntr=0.3,0.1

Type RM Length L Ch R = 1,50934,450,450,450
BEGIN DESCRIPTION:
Stream0095 97.0
END DESCRIPTION:
XS GIS Cut Line= 3
      1766124.96     13896925.02      1766925.00     13896425.00
      1767074.99     13896075.03
#Sta/Elev= 30
  4056.2 2313.10  4085.1 2312.91  4100.5 2310.77  4115.2 2310.85  4164.1 2307.87
  4244.9 2306.23  4289.1 2302.47  4433.6 2294.55  4535.6 2291.02  4586.7 2290.40
  4657.7 2289.65  4798.8 2285.89  4876.4 2285.12  4905.3 2285.80  4913.0 2284.55
  4949.5 2284.07  4958.0 2283.00  4986.1 2281.40  4992.0 2282.29  4994.0 2281.20
  4994.4 2280.70  4999.4 2281.20  5066.7 2284.31  5084.9 2286.47  5166.5 2289.28
  5242.6 2293.46  5266.6 2295.50  5304.3 2299.65  5365.9 2304.90  5380.4 2305.46
#Mann=7,-1,0
  4056.2     0.1       0  4586.7    0.07       0  4798.8     0.1       0
  4958.0    0.07       0  4994.0    0.05       0  4999.4    0.07       0
  5266.6     0.1       0
Bank Sta=4994,4999.4
Exp/Cntr=0.3,0.1

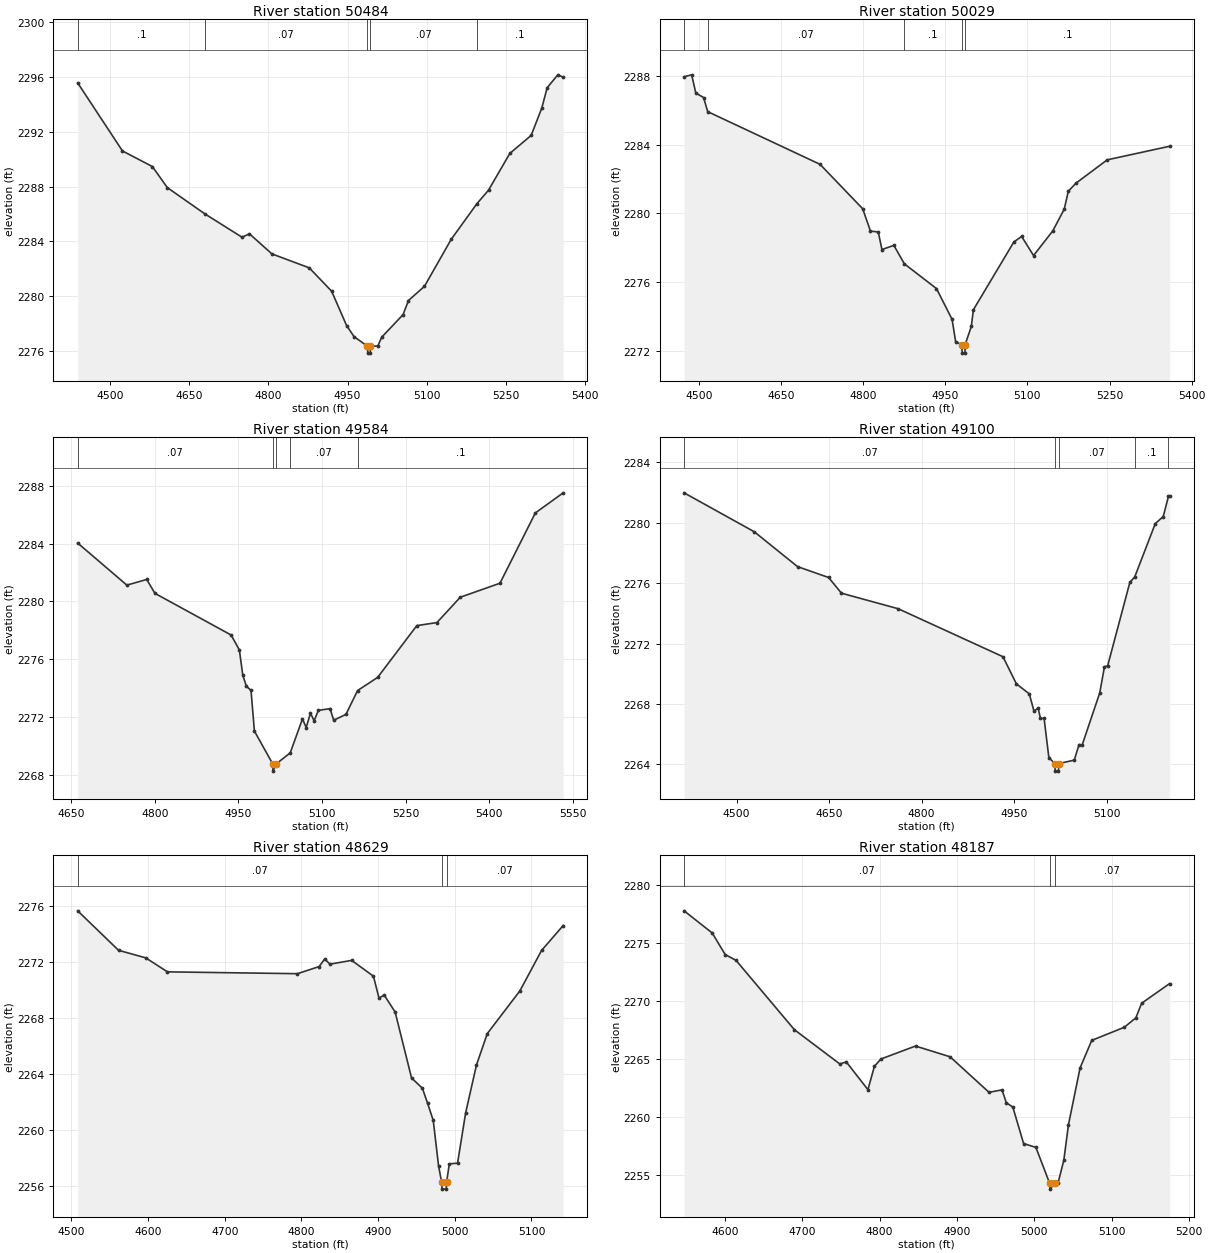
Type RM Length L Ch R = 1,50484,455,455,455
BEGIN DESCRIPTION:
Stream0095 96.0
END DESCRIPTION:
XS GIS Cut Line= 3
      1766925.03     13896974.97      1767325.00     13896575.00
      1767375.00     13896225.00
#Sta/Elev= 30
  4439.0 2295.58  4523.8 2290.60  4580.4 2289.46  4608.7 2287.92  4679.7 2286.00
  4750.1 2284.29  4764.2 2284.54  4806.7 2283.07  4877.4 2282.05  4919.8 2280.34
  4948.1 2277.83  4962.2 2277.02  4987.7 2276.31  4988.2 2275.81  4992.9 2275.81
  4993.3 2276.31  5007.2 2276.33  5014.7 2276.98  5055.1 2278.63  5065.3 2279.66
  5095.6 2280.70  5146.1 2284.13  5194.6 2286.73  5216.8 2287.73  5257.2 2290.42
  5297.6 2291.74  5317.8 2293.75  5327.9 2295.23  5348.1 2296.17  5358.2 2296.00
#Mann=5,-1,0
  4439.0     0.1       0  4679.7    0.07       0  4987.7    0.05       0
  4993.3    0.07       0  5194.6     0.1       0
Bank Sta=4987.7,4993.3
Exp/Cntr=0.3,0.1

Type RM Length L Ch R = 1,50029,445,445,445
BEGIN DESCRIPTION:
Stream0095 95.0
END DESCRIPTION:
XS GIS Cut Line= 3
      1767374.99     13897125.02      1767725.00     13896725.00
      1767988.04     13896486.79
#Sta/Elev= 30
  4473.3 2287.94  4487.1 2288.05  4494.7 2286.99  4508.9 2286.73  4516.4 2285.91
  4721.5 2282.85  4799.3 2280.27  4813.6 2278.97  4827.8 2278.92  4834.5 2277.90
  4856.3 2278.14  4875.4 2277.07  4934.1 2275.63  4962.6 2273.84  4969.2 2272.53
  4980.4 2272.38  4980.9 2271.88  4986.0 2271.88  4986.5 2272.38  4997.7 2273.43
  5001.5 2274.40  5075.4 2278.34  5089.6 2278.66  5111.3 2277.55  5146.4 2278.98
  5167.4 2280.25  5174.8 2281.29  5189.0 2281.76  5245.8 2283.11  5359.7 2283.90
#Mann=5,-1,0
  4473.3     0.1       0  4516.4    0.07       0  4875.4     0.1       0
  4980.4    0.05       0  4986.5     0.1       0
Bank Sta=4980.4,4986.5
Exp/Cntr=0.3,0.1

Type RM Length L Ch R = 1,49584,484,484,484
BEGIN DESCRIPTION:
Stream0095 94.0
END DESCRIPTION:
XS GIS Cut Line= 3
      1767748.44     13897221.17      1768025.00     13897025.00
      1768375.02     13896624.98
#Sta/Elev= 30
  4661.7 2284.04  4749.8 2281.13  4785.5 2281.52  4800.2 2280.56  4936.8 2277.68
  4951.6 2276.65  4957.7 2274.92  4964.0 2274.15  4972.5 2273.85  4978.6 2271.04
  5011.4 2268.77  5011.9 2268.27  5017.7 2268.77  5042.8 2269.53  5064.8 2271.88
  5071.5 2271.28  5079.1 2272.28  5085.7 2271.75  5093.3 2272.47  5114.2 2272.59
  5120.8 2271.79  5142.7 2272.19  5163.6 2273.84  5199.6 2274.75  5269.8 2278.33
  5305.9 2278.54  5347.7 2280.29  5418.9 2281.26  5482.4 2286.12  5532.3 2287.51
#Mann=5,-1,0
  4661.7    0.07       0  5011.4    0.05       0  5017.7    0.07       0
  5042.8    0.07       0  5163.6     0.1       0
Bank Sta=5011.4,5017.7
Exp/Cntr=0.3,0.1

Type RM Length L Ch R = 1,49100,471,471,471
BEGIN DESCRIPTION:
Stream0095 93.0
END DESCRIPTION:
XS GIS Cut Line= 3
      1768092.17     13897462.28      1768475.00     13897025.00
      1768524.99     13896825.04
#Sta/Elev= 30
  4414.9 2281.99  4528.7 2279.41  4598.9 2277.10  4649.2 2276.38  4670.1 2275.34
  4762.1 2274.31  4932.0 2271.13  4953.8 2269.33  4974.7 2268.67  4982.3 2267.52
  4989.0 2267.73  4992.8 2267.04  4998.7 2267.04  5006.4 2264.45  5016.1 2264.05
  5016.6 2263.55  5022.0 2263.55  5022.5 2264.05  5047.6 2264.28  5055.4 2265.31
  5060.5 2265.29  5088.9 2268.73  5096.6 2270.47  5101.7 2270.52  5137.8 2276.06
  5145.7 2276.42  5179.0 2279.95  5191.9 2280.42  5200.4 2281.76  5202.2 2281.76
#Mann=5,-1,0
  4414.9    0.07       0  5016.1    0.05       0  5022.5    0.07       0
  5145.7     0.1       0  5200.4    0.07       0
Bank Sta=5016.1,5022.5
Exp/Cntr=0.3,0.1

Type RM Length L Ch R = 1,48629,442,442,442
BEGIN DESCRIPTION:
Stream0095 92.0
END DESCRIPTION:
XS GIS Cut Line= 3
      1768486.17     13897531.63      1768825.00     13897175.00
      1768924.97     13897075.03
#Sta/Elev= 30
  4508.1 2275.67  4561.4 2272.85  4596.9 2272.31  4625.2 2271.31  4794.8 2271.18
  4823.1 2271.69  4830.3 2272.23  4837.2 2271.86  4865.5 2272.13  4893.9 2271.00
  4901.1 2269.44  4908.0 2269.65  4922.2 2268.44  4943.6 2263.73  4957.7 2263.00
  4964.6 2261.91  4971.9 2260.70  4978.8 2257.47  4982.8 2256.29  4983.3 2255.79
  4988.8 2255.79  4989.3 2256.29  4992.9 2257.60  5003.6 2257.64  5014.2 2261.25
  5028.3 2264.66  5042.4 2266.90  5084.9 2269.95  5113.2 2272.84  5141.4 2274.62
#Mann=3,-1,0
  4508.1    0.07       0  4982.8    0.05       0  4989.3    0.07       0
Bank Sta=4982.8,4989.3
Exp/Cntr=0.3,0.1

Type RM Length L Ch R = 1,48187,446,446,446
BEGIN DESCRIPTION:
Stream0095 91.0
END DESCRIPTION:
XS GIS Cut Line= 3
      1768924.99     13897875.01      1769125.00     13897475.00
      1769225.00     13897325.00
#Sta/Elev= 30
  4547.3 2277.80  4583.7 2275.88  4600.4 2274.02  4614.4 2273.52  4689.9 2267.52
  4748.6 2264.56  4756.9 2264.74  4784.9 2262.34  4793.3 2264.36  4801.7 2264.99
  4846.4 2266.11  4891.1 2265.18  4941.4 2262.11  4958.2 2262.32  4963.8 2261.21
  4972.2 2260.83  4986.1 2257.68  5002.0 2257.35  5019.8 2254.24  5020.3 2253.74
  5026.4 2254.24  5030.6 2254.26  5038.1 2256.24  5044.1 2259.31  5059.1 2264.22
  5074.2 2266.60  5116.2 2267.73  5131.2 2268.55  5138.7 2269.81  5174.8 2271.51
#Mann=3,-1,0
  4547.3    0.07       0  5019.8    0.05       0  5026.4    0.07       0
Bank Sta=5019.8,5026.4
Exp/Cntr=0.3,0.1

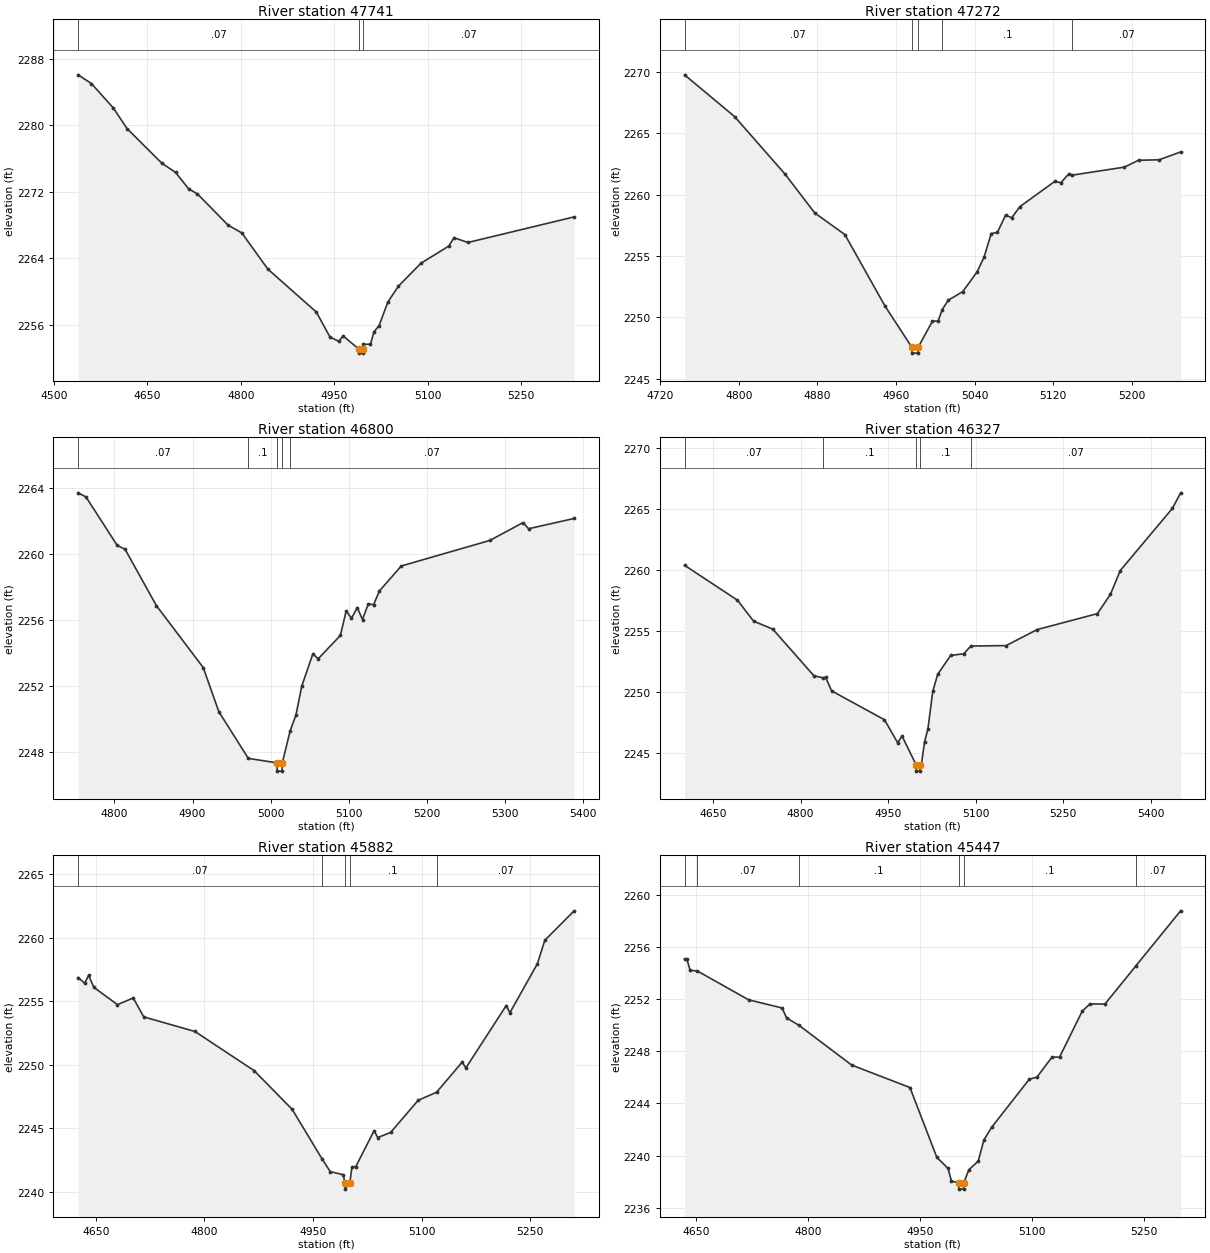
Type RM Length L Ch R = 1,47741,469,469,469
BEGIN DESCRIPTION:
Stream0095 90.0
END DESCRIPTION:
XS GIS Cut Line= 3
      1769025.00     13898125.00      1769375.00     13897825.00
      1769525.00     13897524.99
#Sta/Elev= 30
  4538.8 2286.09  4560.2 2285.04  4595.3 2282.11  4617.3 2279.63  4673.3 2275.45
  4695.2 2274.36  4716.1 2272.39  4730.3 2271.77  4779.7 2268.00  4801.7 2267.07
  4843.4 2262.72  4921.3 2257.55  4943.3 2254.53  4957.5 2254.03  4964.1 2254.69
  4989.3 2253.11  4989.8 2252.61  4995.5 2252.61  4996.0 2253.11  4996.5 2253.67
  5008.2 2253.68  5013.8 2255.17  5022.1 2255.93  5036.1 2258.75  5052.9 2260.65
  5089.2 2263.42  5133.9 2265.49  5142.3 2266.49  5164.7 2265.92  5335.2 2269.00
#Mann=3,-1,0
  4538.8    0.07       0  4989.3    0.05       0  4996.0    0.07       0
Bank Sta=4989.3,4996
Exp/Cntr=0.3,0.1

Type RM Length L Ch R = 1,47272,472,472,472
BEGIN DESCRIPTION:
Stream0095 89.0
END DESCRIPTION:
XS GIS Cut Line= 3
      1769425.00     13898225.00      1769675.00     13898175.00
      1769875.04     13898024.97
#Sta/Elev= 30
  4744.8 2269.78  4795.8 2266.37  4846.8 2261.71  4877.4 2258.51  4908.0 2256.75
  4948.8 2250.93  4976.0 2247.58  4976.5 2247.08  4982.3 2247.08  4982.8 2247.58
  4997.2 2249.69  5002.9 2249.69  5007.1 2250.63  5013.3 2251.40  5027.9 2252.09
  5042.5 2253.69  5049.8 2254.93  5057.0 2256.83  5063.3 2256.93  5071.6 2258.33
  5077.9 2258.13  5086.2 2259.03  5121.6 2261.08  5127.9 2260.98  5136.2 2261.72
  5139.6 2261.60  5192.5 2262.25  5207.0 2262.81  5227.9 2262.85  5249.8 2263.49
#Mann=5,-1,0
  4744.8    0.07       0  4976.0    0.05       0  4982.8    0.07       0
  5007.1     0.1       0  5139.6    0.07       0
Bank Sta=4976,4982.8
Exp/Cntr=0.3,0.1

Type RM Length L Ch R = 1,46800,473,473,473
BEGIN DESCRIPTION:
Stream0095 88.0
END DESCRIPTION:
XS GIS Cut Line= 4
      1769624.92     13898581.20      1769848.06     13898581.20
      1769875.00     13898575.00      1770157.98     13898315.55
#Sta/Elev= 30
  4753.6 2263.68  4763.7 2263.43  4803.7 2260.50  4813.7 2260.27  4853.7 2256.87
  4913.7 2253.12  4933.7 2250.45  4971.4 2247.63  5008.0 2247.36  5008.5 2246.86
  5014.4 2246.86  5014.9 2247.36  5024.9 2249.29  5032.4 2250.26  5039.8 2252.00
  5054.0 2253.95  5060.8 2253.65  5089.2 2255.06  5096.6 2256.54  5103.4 2256.10
  5110.8 2256.74  5117.5 2256.02  5124.9 2256.97  5131.7 2256.92  5139.1 2257.75
  5167.2 2259.26  5280.3 2260.80  5322.9 2261.88  5330.0 2261.51  5388.3 2262.13
#Mann=5,-1,0
  4753.6    0.07       0  4971.4     0.1       0  5008.0    0.05       0
  5014.9     0.1       0  5024.9    0.07       0
Bank Sta=5008,5014.9
Exp/Cntr=0.3,0.1

Type RM Length L Ch R = 1,46327,445,445,445
BEGIN DESCRIPTION:
Stream0095 87.0
END DESCRIPTION:
XS GIS Cut Line= 3
      1769674.97     13898925.00      1770075.00     13898975.00
      1770475.04     13899175.02
#Sta/Elev= 30
  4601.1 2260.35  4691.8 2257.49  4719.5 2255.77  4752.3 2255.12  4822.8 2251.30
  4838.2 2251.13  4843.0 2251.17  4853.1 2250.06  4943.8 2247.69  4966.4 2245.81
  4974.0 2246.35  4998.2 2243.98  4998.7 2243.48  5004.7 2243.48  5005.2 2243.98
  5007.0 2243.98  5012.6 2245.90  5018.2 2246.91  5026.6 2250.01  5035.0 2251.41
  5057.3 2252.96  5079.7 2253.10  5091.8 2253.73  5152.4 2253.77  5205.5 2255.08
  5308.9 2256.39  5331.3 2257.98  5348.0 2259.92  5437.5 2265.02  5451.5 2266.29
#Mann=5,-1,0
  4601.1    0.07       0  4838.2     0.1       0  4998.2    0.05       0
  5005.2     0.1       0  5091.8    0.07       0
Bank Sta=4998.2,5005.2
Exp/Cntr=0.3,0.1

Type RM Length L Ch R = 1,45882,435,435,435
BEGIN DESCRIPTION:
Stream0095 86.0
END DESCRIPTION:
XS GIS Cut Line= 3
      1769675.01     13899225.00      1770025.00     13899375.00
      1770324.99     13899425.00
#Sta/Elev= 30
  4625.6 2256.88  4634.7 2256.43  4640.1 2257.05  4647.3 2256.11  4680.0 2254.74
  4701.7 2255.27  4716.3 2253.78  4787.0 2252.63  4868.6 2249.55  4921.2 2246.50
  4962.1 2242.63  4973.7 2241.60  4991.9 2241.35  4993.8 2240.72  4994.3 2240.22
  5000.8 2240.72  5003.7 2241.98  5008.9 2241.98  5034.3 2244.82  5039.3 2244.28
  5057.1 2244.68  5095.1 2247.21  5120.6 2247.85  5155.9 2250.22  5161.0 2249.76
  5216.7 2254.67  5221.8 2254.11  5259.8 2257.97  5270.0 2259.81  5310.5 2262.13
#Mann=5,-1,0
  4625.6    0.07       0  4962.1     0.1       0  4993.8    0.05       0
  5000.8     0.1       0  5120.6    0.07       0
Bank Sta=4993.8,5000.8
Exp/Cntr=0.3,0.1

Type RM Length L Ch R = 1,45447,446,446,446
BEGIN DESCRIPTION:
Stream0095 85.0
END DESCRIPTION:
XS GIS Cut Line= 3
      1769624.98     13899574.99      1769925.00     13899775.00
      1770224.98     13899825.00
#Sta/Elev= 30
  4634.7 2255.07  4637.7 2255.07  4642.2 2254.19  4651.7 2254.15  4720.4 2251.94
  4765.4 2251.31  4771.4 2250.55  4788.1 2249.98  4858.6 2246.94  4936.7 2245.22
  4972.7 2239.88  4987.8 2239.02  4992.3 2238.05  5001.8 2237.94  5002.3 2237.44
  5008.5 2237.44  5009.0 2237.94  5015.6 2238.92  5028.2 2239.58  5035.8 2241.20
  5046.0 2242.16  5096.7 2245.86  5106.8 2246.01  5127.1 2247.55  5137.2 2247.55
  5167.6 2251.07  5177.8 2251.62  5198.0 2251.61  5239.5 2254.54  5299.4 2258.75
#Mann=6,-1,0
  4634.7     0.1       0  4651.7    0.07       0  4788.1     0.1       0
  5001.8    0.05       0  5009.0     0.1       0  5239.5    0.07       0
Bank Sta=5001.8,5009
Exp/Cntr=0.3,0.1

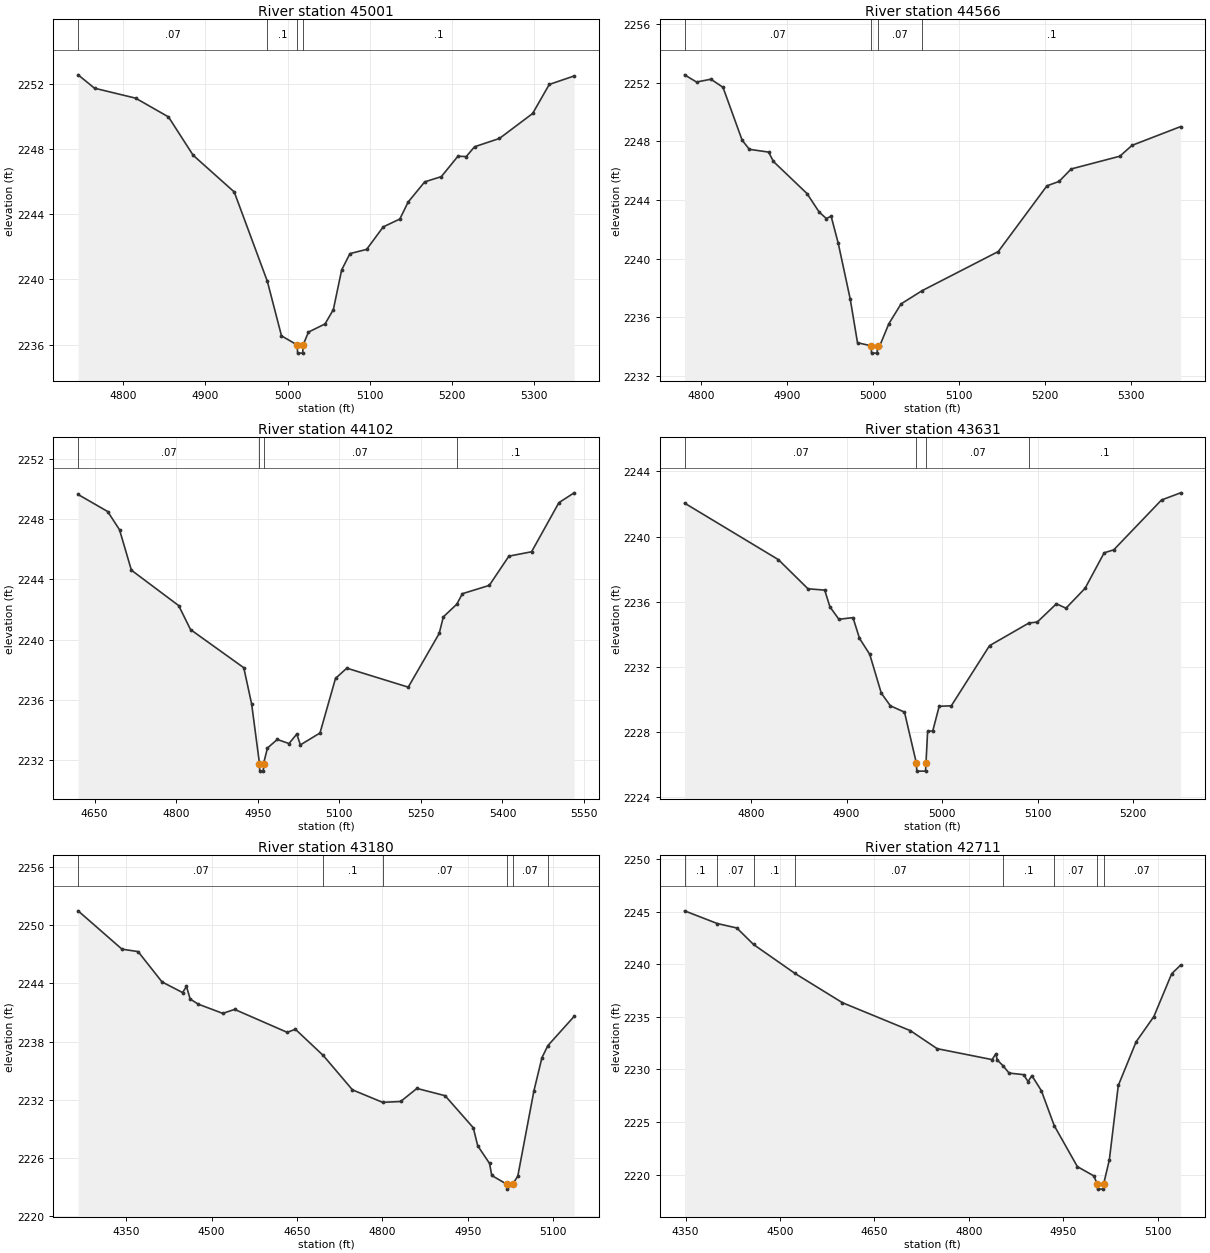
Type RM Length L Ch R = 1,45001,435,435,435
BEGIN DESCRIPTION:
Stream0095 84.0
END DESCRIPTION:
XS GIS Cut Line= 3
      1769524.96     13900175.00      1769775.00     13900175.00
      1770125.01     13900125.00
#Sta/Elev= 30
  4745.0 2252.54  4765.0 2251.72  4815.0 2251.11  4855.0 2249.96  4885.0 2247.61
  4935.0 2245.36  4975.3 2239.88  4992.5 2236.54  5011.6 2235.98  5012.1 2235.48
  5018.3 2235.48  5018.8 2235.98  5025.3 2236.77  5045.5 2237.27  5055.6 2238.15
  5065.7 2240.58  5075.8 2241.58  5096.1 2241.84  5116.3 2243.22  5136.5 2243.70
  5146.6 2244.74  5166.8 2245.98  5187.0 2246.30  5207.2 2247.55  5217.3 2247.53
  5227.4 2248.13  5257.7 2248.64  5298.1 2250.17  5318.3 2251.95  5348.6 2252.47
#Mann=4,-1,0
  4745.0    0.07       0  4975.3     0.1       0  5011.6    0.05       0
  5018.8     0.1       0
Bank Sta=5011.6,5018.8
Exp/Cntr=0.3,0.1

Type RM Length L Ch R = 1,44566,464,464,464
BEGIN DESCRIPTION:
Stream0095 83.0
END DESCRIPTION:
XS GIS Cut Line= 3
      1769675.03     13900674.98      1769875.00     13900575.00
      1770124.98     13900325.02
#Sta/Elev= 30
  4781.0 2252.53  4794.9 2252.04  4811.7 2252.23  4825.7 2251.68  4848.0 2248.07
  4856.4 2247.45  4878.8 2247.26  4884.4 2246.62  4923.5 2244.43  4937.5 2243.18
  4945.9 2242.73  4951.5 2242.89  4959.8 2241.04  4973.8 2237.22  4982.2 2234.26
  4998.0 2234.05  4998.5 2233.55  5005.0 2233.55  5005.5 2234.05  5008.1 2234.05
  5018.7 2235.56  5032.9 2236.91  5057.4 2237.81  5146.0 2240.48  5202.6 2244.96
  5216.7 2245.26  5230.8 2246.11  5287.4 2246.98  5301.6 2247.72  5358.1 2249.00
#Mann=4,-1,0
  4781.0    0.07       0  4998.0    0.05       0  5005.5    0.07       0
  5057.4     0.1       0
Bank Sta=4998,5005.5
Exp/Cntr=0.3,0.1

Type RM Length L Ch R = 1,44102,471,471,471
BEGIN DESCRIPTION:
Stream0095 82.0
END DESCRIPTION:
XS GIS Cut Line= 3
      1769924.99     13901325.03      1770075.00     13900975.00
      1770424.98     13900575.03
#Sta/Elev= 30
  4619.5 2249.62  4673.9 2248.49  4695.7 2247.28  4717.5 2244.60  4804.5 2242.25
  4826.3 2240.66  4924.2 2238.13  4938.7 2235.72  4953.1 2231.77  4953.6 2231.27
  4960.1 2231.27  4960.6 2231.77  4967.7 2232.80  4985.8 2233.37  5007.4 2233.10
  5021.7 2233.73  5028.3 2233.01  5064.4 2233.80  5092.9 2237.42  5113.7 2238.10
  5226.7 2236.84  5283.6 2240.40  5291.2 2241.50  5315.9 2242.34  5326.3 2243.04
  5375.7 2243.59  5411.8 2245.53  5453.5 2245.82  5503.8 2249.08  5531.8 2249.73
#Mann=4,-1,0
  4619.5    0.07       0  4953.1    0.05       0  4960.6    0.07       0
  5315.9     0.1       0
Bank Sta=4953.1,4960.6
Exp/Cntr=0.3,0.1

Type RM Length L Ch R = 1,43631,451,451,451
BEGIN DESCRIPTION:
Stream0095 81.0
END DESCRIPTION:
XS GIS Cut Line= 3
      1770425.01     13901274.97      1770525.00     13901025.00
      1770525.00     13900775.02
#Sta/Elev= 30
  4730.4 2242.06  4828.6 2238.59  4859.6 2236.80  4877.1 2236.72  4882.5 2235.70
  4891.9 2234.93  4906.7 2235.03  4913.5 2233.76  4924.2 2232.78  4936.3 2230.40
  4945.8 2229.62  4960.6 2229.23  4973.0 2226.11  4973.5 2225.61  4982.6 2225.61
  4983.1 2226.11  4984.8 2228.05  4990.2 2228.08  4996.9 2229.59  5009.6 2229.62
  5049.6 2233.31  5090.8 2234.70  5099.6 2234.76  5119.6 2235.88  5129.6 2235.61
  5149.6 2236.83  5169.6 2239.01  5179.6 2239.19  5229.6 2242.25  5249.6 2242.69
#Mann=4,-1,0
  4730.4    0.07       0  4973.0    0.05       0  4983.1    0.07       0
  5090.8     0.1       0
Bank Sta=4973,4983.1
Exp/Cntr=0.3,0.1

Type RM Length L Ch R = 1,43180,469,469,469
BEGIN DESCRIPTION:
Stream0095 80.0
END DESCRIPTION:
XS GIS Cut Line= 3
      1770457.98     13901636.01      1770925.00     13901075.00
      1771025.01     13900974.99
#Sta/Elev= 30
  4265.4 2251.50  4342.5 2247.54  4370.8 2247.29  4412.8 2244.16  4448.9 2243.06
  4455.8 2243.69  4462.3 2242.39  4476.6 2241.86  4519.5 2240.91  4540.4 2241.32
  4632.8 2238.95  4647.1 2239.27  4696.1 2236.56  4747.4 2233.01  4800.5 2231.72
  4832.0 2231.81  4860.6 2233.16  4910.1 2232.41  4959.6 2229.10  4967.4 2227.24
  4988.2 2225.41  4992.1 2224.17  5018.6 2223.26  5019.1 2222.76  5028.7 2223.26
  5037.8 2224.10  5066.1 2232.90  5080.2 2236.33  5090.6 2237.58  5136.8 2240.60
#Mann=6,-1,0
  4265.4    0.07       0  4696.1     0.1       0  4800.5    0.07       0
  5018.6    0.05       0  5028.7    0.07       0  5090.6     0.1       0
Bank Sta=5018.6,5028.7
Exp/Cntr=0.3,0.1

Type RM Length L Ch R = 1,42711,443,443,443
BEGIN DESCRIPTION:
Stream0095 79.0
END DESCRIPTION:
XS GIS Cut Line= 3
      1770968.50     13901814.26      1771325.00     13901275.00
      1771425.02     13901174.98
#Sta/Elev= 30
  4348.5 2245.07  4400.6 2243.86  4431.5 2243.44  4458.1 2241.87  4523.9 2239.12
  4599.2 2236.34  4707.2 2233.68  4749.7 2231.97  4837.0 2230.93  4843.0 2231.49
  4845.1 2230.90  4854.1 2230.36  4864.0 2229.65  4887.1 2229.50  4894.1 2228.84
  4900.1 2229.41  4915.2 2227.98  4935.7 2224.65  4972.4 2220.76  4998.5 2219.88
  5003.9 2219.12  5004.4 2218.62  5013.7 2218.62  5014.2 2219.12  5023.2 2221.40
  5037.4 2228.47  5065.7 2232.62  5093.9 2235.02  5122.2 2239.09  5136.4 2239.91
#Mann=8,-1,0
  4348.5     0.1       0  4400.6    0.07       0  4458.1     0.1       0
  4523.9    0.07       0  4854.1     0.1       0  4935.7    0.07       0
  5003.9    0.05       0  5014.2    0.07       0
Bank Sta=5003.9,5014.2
Exp/Cntr=0.3,0.1

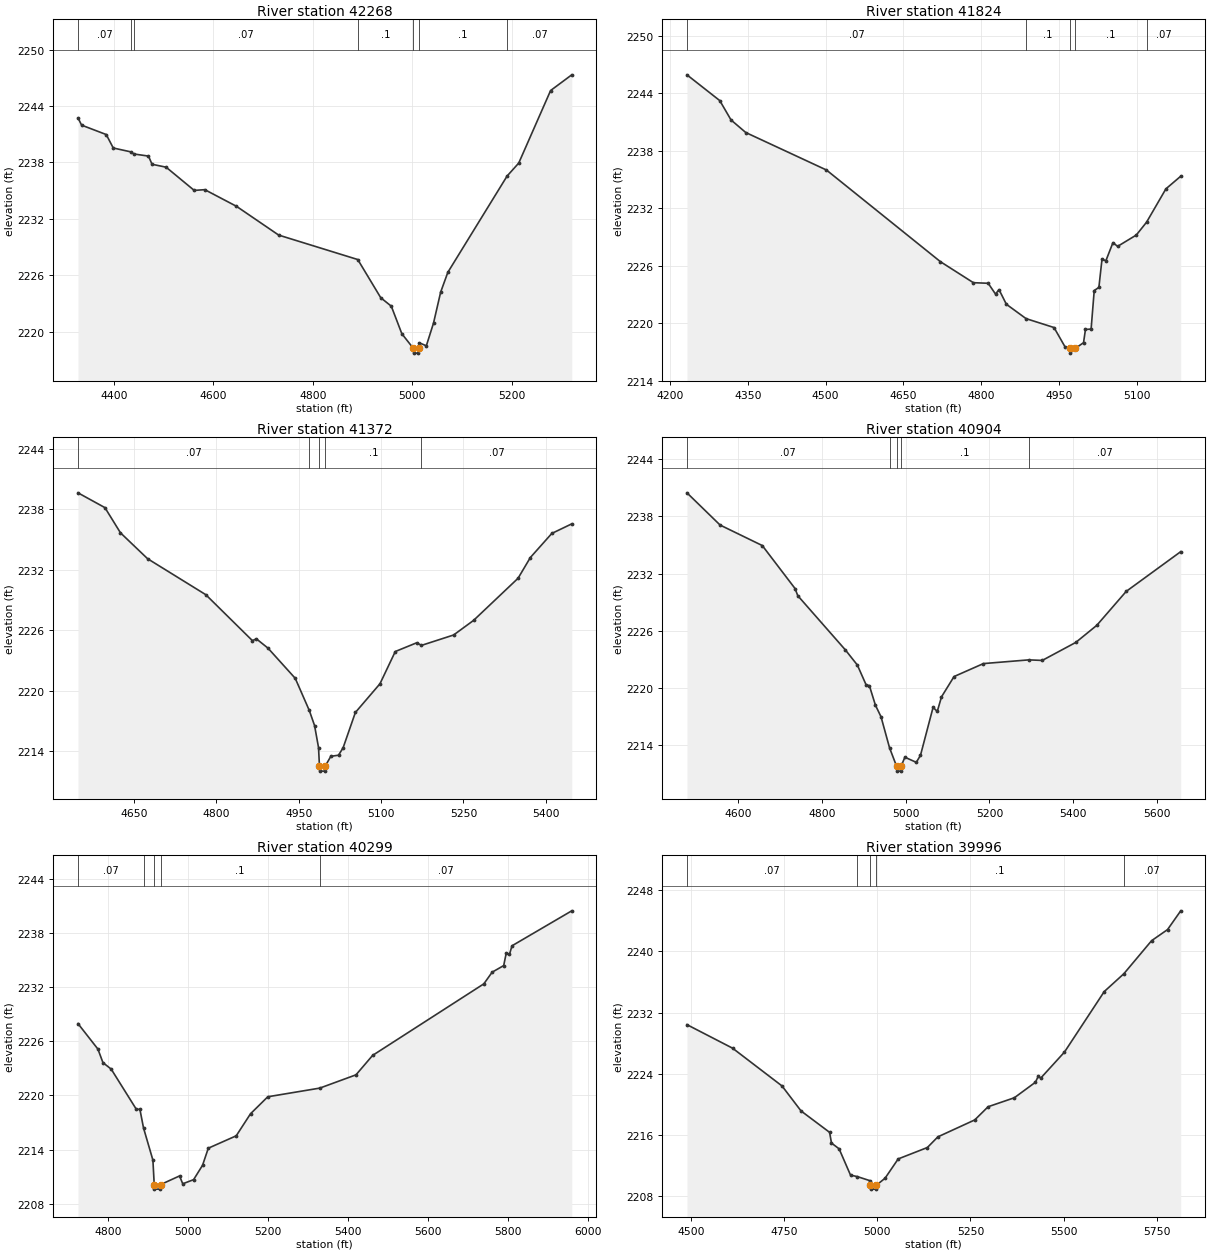
Type RM Length L Ch R = 1,42268,444,444,444
BEGIN DESCRIPTION:
Stream0095 78.0
END DESCRIPTION:
XS GIS Cut Line= 3
      1771197.22     13901997.57      1771675.00     13901525.00
      1771875.02     13901274.97
#Sta/Elev= 30
  4328.2 2242.73  4335.5 2241.96  4385.0 2240.96  4399.1 2239.53  4434.3 2239.12
  4441.0 2238.89  4469.9 2238.67  4477.0 2237.80  4505.3 2237.49  4561.8 2235.02
  4583.0 2235.10  4646.7 2233.33  4731.5 2230.27  4890.4 2227.67  4936.6 2223.61
  4957.8 2222.71  4979.0 2219.78  5002.2 2218.22  5002.7 2217.72  5012.1 2217.72
  5012.6 2218.22  5013.8 2218.82  5028.2 2218.50  5042.6 2220.91  5057.0 2224.21
  5071.4 2226.31  5190.5 2236.55  5213.9 2237.93  5277.9 2245.64  5320.4 2247.31
#Mann=7,-1,0
  4328.2    0.07       0  4434.3     0.1       0  4441.0    0.07       0
  4890.4     0.1       0  5002.2    0.05       0  5012.6     0.1       0
  5190.5    0.07       0
Bank Sta=5002.2,5012.6
Exp/Cntr=0.3,0.1

Type RM Length L Ch R = 1,41824,452,452,452
BEGIN DESCRIPTION:
Stream0095 77.0
END DESCRIPTION:
XS GIS Cut Line= 3
      1771399.15     13902338.86      1771975.00     13901825.00
      1772075.02     13901674.97
#Sta/Elev= 30
  4232.6 2245.92  4295.9 2243.23  4317.6 2241.21  4346.0 2239.90  4501.5 2235.99
  4721.4 2226.42  4784.9 2224.23  4813.4 2224.17  4827.6 2223.04  4834.3 2223.51
  4848.5 2221.98  4886.5 2220.48  4940.4 2219.55  4962.2 2217.48  4971.2 2217.38
  4971.7 2216.88  4981.6 2217.38  4997.3 2217.97  5001.0 2219.35  5011.9 2219.39
  5017.9 2223.41  5026.9 2223.74  5032.9 2226.68  5040.4 2226.52  5054.0 2228.41
  5063.0 2228.02  5099.0 2229.20  5118.8 2230.54  5156.1 2234.02  5184.7 2235.34
#Mann=5,-1,0
  4232.6    0.07       0  4886.5     0.1       0  4971.2    0.05       0
  4981.6     0.1       0  5118.8    0.07       0
Bank Sta=4971.2,4981.6
Exp/Cntr=0.3,0.1

Type RM Length L Ch R = 1,41372,468,468,468
BEGIN DESCRIPTION:
Stream0095 76.0
END DESCRIPTION:
XS GIS Cut Line= 3
      1771798.98     13902538.25      1772125.00     13902225.00
      1772324.98     13901825.03
#Sta/Elev= 30
  4547.9 2239.64  4597.0 2238.17  4625.3 2235.67  4674.7 2233.10  4780.7 2229.53
  4865.6 2224.97  4872.8 2225.15  4893.9 2224.23  4943.6 2221.23  4969.2 2218.04
  4978.8 2216.54  4986.0 2214.36  4987.7 2212.52  4988.2 2212.02  4997.7 2212.02
  4998.2 2212.52  5008.4 2213.49  5022.4 2213.60  5030.8 2214.34  5053.1 2217.84
  5097.9 2220.69  5125.8 2223.89  5164.9 2224.76  5173.5 2224.50  5232.0 2225.53
  5268.4 2226.98  5349.4 2231.16  5371.8 2233.22  5410.9 2235.61  5447.2 2236.56
#Mann=5,-1,0
  4547.9    0.07       0  4969.2     0.1       0  4987.7    0.05       0
  4998.2     0.1       0  5173.5    0.07       0
Bank Sta=4987.7,4998.2
Exp/Cntr=0.3,0.1

Type RM Length L Ch R = 1,40904,605,605,605
BEGIN DESCRIPTION:
Stream0095 75.0
END DESCRIPTION:
XS GIS Cut Line= 3
      1772063.82     13902856.10      1772475.00     13902525.00
      1772425.00     13901875.04
#Sta/Elev= 30
  4477.2 2240.47  4556.4 2237.09  4657.2 2234.94  4735.5 2230.43  4742.0 2229.68
  4855.6 2224.00  4884.3 2222.41  4905.2 2220.34  4913.1 2220.24  4927.5 2218.20
  4940.9 2216.98  4961.3 2213.72  4978.2 2211.78  4978.7 2211.28  4988.3 2211.28
  4988.8 2211.78  4997.9 2212.74  5025.2 2212.20  5035.2 2212.94  5065.3 2217.97
  5075.3 2217.54  5085.4 2219.07  5115.4 2221.20  5185.6 2222.56  5294.1 2222.95
  5326.1 2222.89  5406.3 2224.78  5456.4 2226.57  5526.7 2230.13  5657.0 2234.30
#Mann=5,-1,0
  4477.2    0.07       0  4961.3     0.1       0  4978.2    0.05       0
  4988.8     0.1       0  5294.1    0.07       0
Bank Sta=4978.2,4988.8
Exp/Cntr=0.3,0.1

Type RM Length L Ch R = 1,40299,303,303,303
BEGIN DESCRIPTION:
Stream0095 74.0
END DESCRIPTION:
XS GIS Cut Line= 3
      1772675.04     13902924.99      1772897.04     13902859.49
      1773524.98     13902075.02
#Sta/Elev= 30
  4723.8 2227.95  4773.7 2225.13  4786.3 2223.63  4807.0 2222.91  4869.7 2218.48
  4878.9 2218.45  4887.9 2216.40  4911.4 2212.84  4914.7 2210.13  4915.2 2209.63
  4930.0 2209.63  4930.5 2210.13  4978.1 2211.09  4986.1 2210.22  5013.3 2210.68
  5035.7 2212.27  5050.1 2214.16  5120.0 2215.53  5155.8 2217.97  5199.0 2219.85
  5329.2 2220.81  5419.9 2222.28  5461.5 2224.43  5740.0 2232.35  5760.8 2233.64
  5789.7 2234.37  5796.1 2235.76  5804.1 2235.60  5810.5 2236.56  5960.1 2240.43
#Mann=5,-1,0
  4723.8    0.07       0  4887.9     0.1       0  4914.7    0.05       0
  4930.5     0.1       0  5329.2    0.07       0
Bank Sta=4914.7,4930.5
Exp/Cntr=0.3,0.1

Type RM Length L Ch R = 1,39996,437,437,437
BEGIN DESCRIPTION:
Stream0095 73.0
END DESCRIPTION:
XS GIS Cut Line= 3
      1772625.03     13903124.99      1773125.00     13903025.00
      1773724.99     13902475.01
#Sta/Elev= 30
  4489.9 2230.42  4612.2 2227.35  4744.8 2222.42  4795.8 2219.16  4872.3 2216.37
  4877.4 2214.97  4897.8 2214.22  4928.4 2210.79  4946.9 2210.59  4979.4 2210.08
  4981.7 2209.46  4982.2 2208.96  4997.0 2208.96  4997.5 2209.46  5021.0 2210.38
  5056.2 2212.90  5134.5 2214.39  5162.6 2215.78  5261.5 2217.99  5297.3 2219.71
  5367.6 2220.88  5424.3 2222.91  5431.7 2223.69  5438.5 2223.45  5502.0 2226.84
  5608.7 2234.74  5661.2 2237.06  5735.7 2241.38  5778.3 2242.82  5813.7 2245.27
#Mann=5,-1,0
  4489.9    0.07       0  4946.9     0.1       0  4981.7    0.05       0
  4997.5     0.1       0  5661.2    0.07       0
Bank Sta=4981.7,4997.5
Exp/Cntr=0.3,0.1