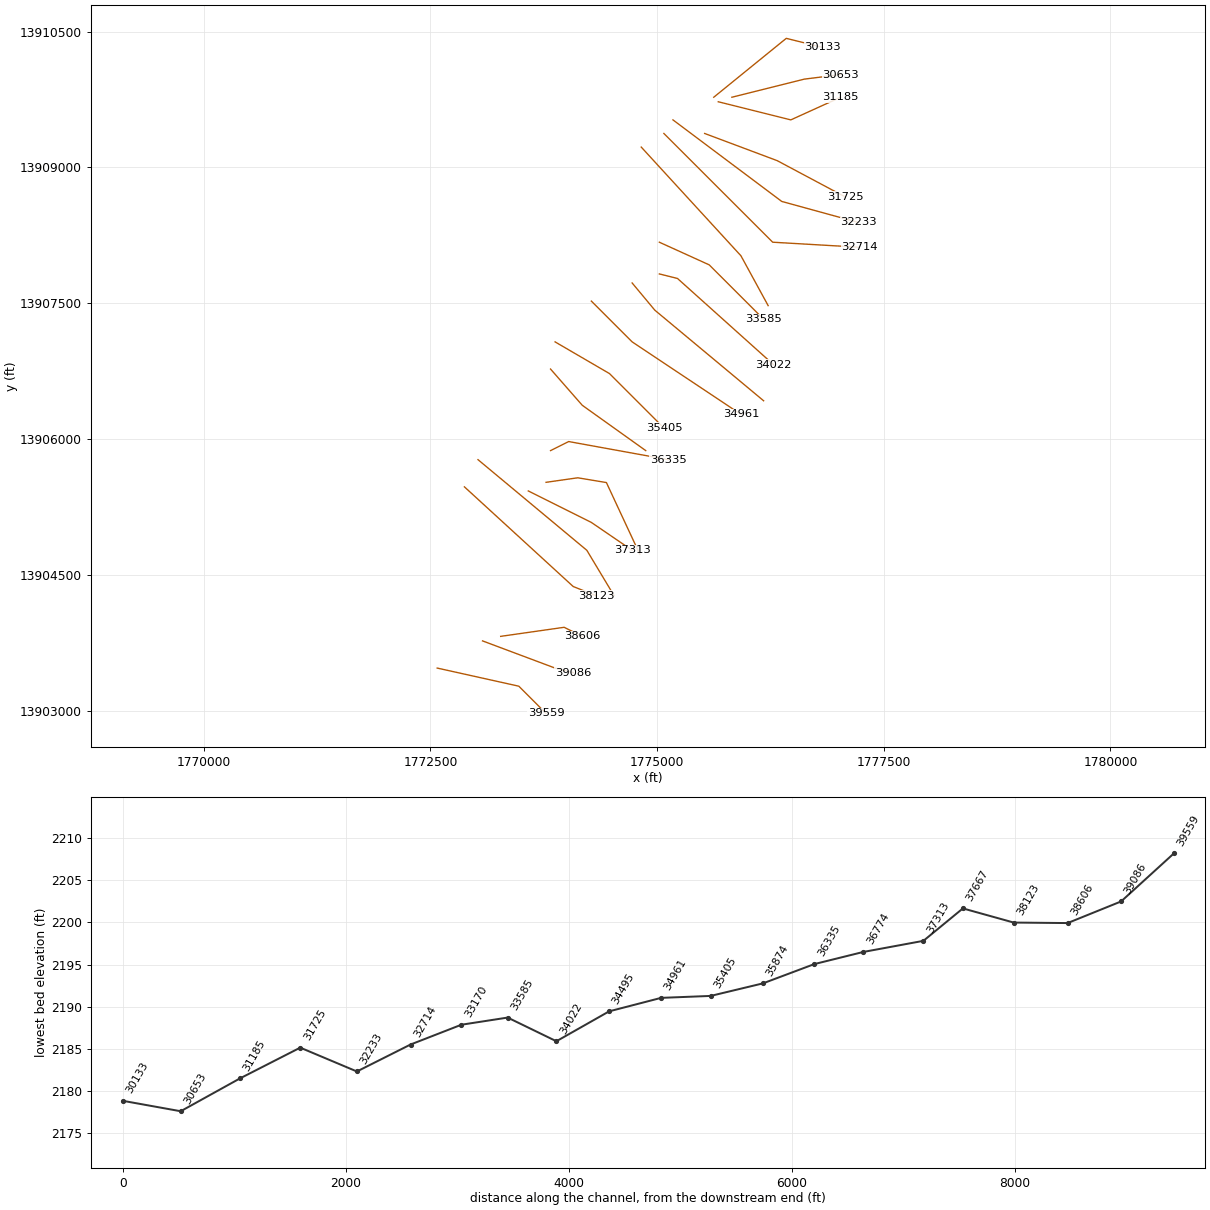
HEC-RAS study Stream0095.prj: Stream0095 Base Level Engineering

--- Stream0095.g01 (geometry) --- (continued)

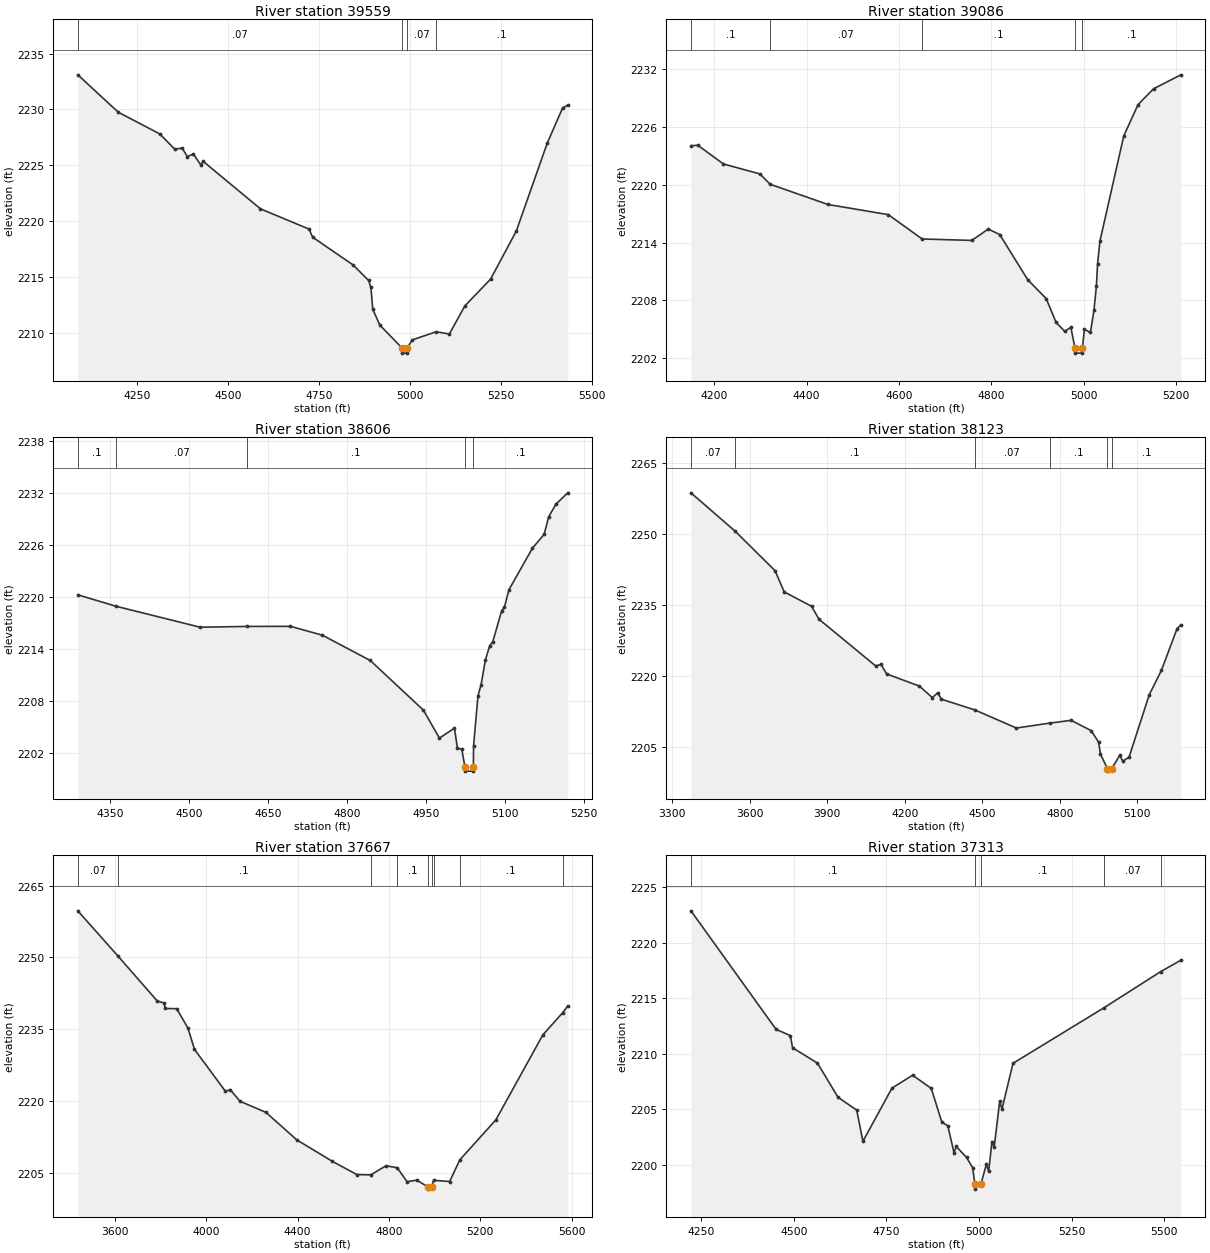
Type RM Length L Ch R = 1,39559,473,473,473
BEGIN DESCRIPTION:
Stream0095 72.0
END DESCRIPTION:
XS GIS Cut Line= 3
      1772575.01     13903475.00      1773475.00     13903275.00
      1773774.99     13902975.01
#Sta/Elev= 30
  4087.5 2233.10  4198.9 2229.75  4312.9 2227.81  4353.8 2226.45  4374.3 2226.54
  4388.4 2225.78  4405.1 2226.02  4425.5 2225.03  4431.9 2225.36  4589.4 2221.11
  4722.6 2219.30  4732.9 2218.57  4844.3 2216.08  4886.5 2214.70  4892.9 2214.08
  4898.0 2212.12  4917.3 2210.71  4977.2 2208.70  4977.7 2208.20  4992.6 2208.20
  4993.1 2208.70  5006.9 2209.39  5072.3 2210.11  5108.4 2209.91  5150.9 2212.42
  5221.6 2214.82  5292.3 2219.12  5377.1 2226.97  5419.6 2230.14  5433.7 2230.38
#Mann=4,-1,0
  4087.5    0.07       0  4977.2    0.05       0  4993.1    0.07       0
  5072.3     0.1       0
Bank Sta=4977.2,4993.1
Exp/Cntr=0.3,0.1

Type RM Length L Ch R = 1,39086,480,480,480
BEGIN DESCRIPTION:
Stream0095 71.0
END DESCRIPTION:
XS GIS Cut Line= 3
      1773074.99     13903775.00      1773875.00     13903475.00
      1774075.03     13903424.99
#Sta/Elev= 30
  4149.7 2224.07  4164.8 2224.11  4220.0 2222.17  4299.2 2221.13  4321.1 2220.06
  4446.1 2217.96  4576.9 2216.90  4650.2 2214.37  4757.6 2214.22  4793.2 2215.40
  4818.1 2214.83  4878.6 2210.14  4918.7 2208.17  4940.0 2205.70  4958.7 2204.77
  4972.1 2205.18  4981.0 2203.00  4981.5 2202.50  4996.5 2202.50  4997.0 2203.00
  5001.4 2204.97  5014.4 2204.65  5022.1 2206.95  5027.3 2209.44  5029.9 2211.79
  5035.0 2214.15  5086.6 2225.09  5117.5 2228.34  5151.0 2229.99  5210.3 2231.44
#Mann=5,-1,0
  4149.7     0.1       0  4321.1    0.07       0  4650.2     0.1       0
  4981.0    0.05       0  4997.0     0.1       0
Bank Sta=4981,4997
Exp/Cntr=0.3,0.1

Type RM Length L Ch R = 1,38606,483,483,483
BEGIN DESCRIPTION:
Stream0095 70.0
END DESCRIPTION:
XS GIS Cut Line= 3
      1773275.02     13903825.00      1773975.00     13903925.00
      1774175.01     13903825.00
#Sta/Elev= 30
  4288.8 2220.28  4361.4 2218.96  4521.1 2216.54  4610.1 2216.63  4692.8 2216.64
  4753.4 2215.62  4844.4 2212.70  4945.4 2206.96  4975.7 2203.74  5004.3 2204.89
  5009.9 2202.58  5018.2 2202.45  5024.2 2200.43  5024.7 2199.93  5039.7 2199.93
  5040.2 2200.43  5040.6 2202.85  5049.0 2208.64  5054.6 2209.83  5063.0 2212.74
  5071.3 2214.42  5076.9 2214.83  5093.7 2218.39  5099.3 2218.87  5107.7 2220.86
  5152.4 2225.66  5174.8 2227.27  5183.2 2229.28  5197.1 2230.75  5219.5 2232.05
#Mann=5,-1,0
  4288.8     0.1       0  4361.4    0.07       0  4610.1     0.1       0
  5024.2    0.05       0  5040.2     0.1       0
Bank Sta=5024.2,5040.2
Exp/Cntr=0.3,0.1

Type RM Length L Ch R = 1,38123,456,456,456
BEGIN DESCRIPTION:
Stream0095 69.0
END DESCRIPTION:
XS GIS Cut Line= 3
      1772874.98     13905475.01      1774075.00     13904375.00
      1774325.04     13904274.99
#Sta/Elev= 30
  3372.2 2258.62  3543.3 2250.54  3697.8 2242.22  3733.3 2237.75  3839.3 2234.71
  3867.7 2232.00  4087.2 2222.16  4108.2 2222.46  4129.7 2220.47  4256.8 2217.90
  4306.7 2215.48  4327.7 2216.49  4341.9 2215.14  4470.7 2212.90  4632.3 2209.07
  4760.7 2210.10  4844.4 2210.69  4922.1 2208.52  4950.5 2206.09  4957.9 2203.59
  4985.0 2200.49  4985.5 2199.99  5001.0 2200.49  5032.4 2203.29  5044.5 2202.07
  5068.8 2202.97  5146.8 2216.08  5194.0 2221.22  5254.6 2230.03  5269.4 2230.79
#Mann=6,-1,0
  3372.2    0.07       0  3543.3     0.1       0  4470.7    0.07       0
  4760.7     0.1       0  4985.0    0.05       0  5001.0     0.1       0
Bank Sta=4985,5001
Exp/Cntr=0.3,0.1

Type RM Length L Ch R = 1,37667,354,354,354
BEGIN DESCRIPTION:
Stream0095 68.0
END DESCRIPTION:
XS GIS Cut Line= 3
      1773025.02     13905774.98      1774225.00     13904775.00
      1774524.99     13904275.02
#Sta/Elev= 30
  3437.7 2259.72  3612.3 2250.36  3785.9 2240.90  3814.5 2240.50  3821.0 2239.35
  3870.5 2239.31  3920.0 2235.26  3948.6 2230.81  4084.0 2222.08  4104.8 2222.43
  4147.8 2219.99  4261.0 2217.69  4396.4 2211.95  4552.6 2207.45  4659.3 2204.71
  4720.5 2204.64  4786.9 2206.54  4836.0 2206.14  4879.3 2203.22  4921.6 2203.54
  4969.8 2202.17  4970.3 2201.67  4986.7 2202.17  4995.4 2203.51  5065.8 2203.26
  5110.3 2207.78  5267.9 2216.11  5474.0 2233.86  5560.3 2238.45  5582.8 2239.88
#Mann=9,-1,0
  3437.7    0.07       0  3612.3     0.1       0  4720.5    0.07       0
  4836.0     0.1       0  4969.8    0.05       0  4986.7     0.1       0
  4995.4    0.07       0  5110.3     0.1       0  5560.3    0.07       0
Bank Sta=4969.8,4986.7
Exp/Cntr=0.3,0.1

Type RM Length L Ch R = 1,37313,539,539,539
BEGIN DESCRIPTION:
Stream0095 67.0
END DESCRIPTION:
XS GIS Cut Line= 3
      1773579.57     13905429.81      1774274.91     13905082.46
      1774725.04     13904774.97
#Sta/Elev= 30
  4222.5 2222.86  4452.1 2212.20  4490.9 2211.63  4496.8 2210.54  4563.9 2209.16
  4619.5 2206.08  4669.9 2204.93  4686.6 2202.12  4765.1 2206.91  4820.8 2208.07
  4871.2 2206.88  4899.3 2203.88  4915.9 2203.50  4932.7 2201.06  4938.3 2201.67
  4966.3 2200.67  4983.0 2199.74  4988.6 2198.32  4989.1 2197.82  5005.5 2198.32
  5020.0 2200.08  5026.0 2199.41  5034.9 2202.10  5040.9 2201.58  5055.8 2205.74
  5061.9 2205.02  5091.7 2209.14  5337.8 2214.15  5490.3 2217.39  5544.9 2218.42
#Mann=5,-1,0
  4222.5     0.1       0  4988.6    0.05       0  5005.5     0.1       0
  5337.8    0.07       0  5490.3     0.1       0
Bank Sta=4988.6,5005.5
Exp/Cntr=0.3,0.1

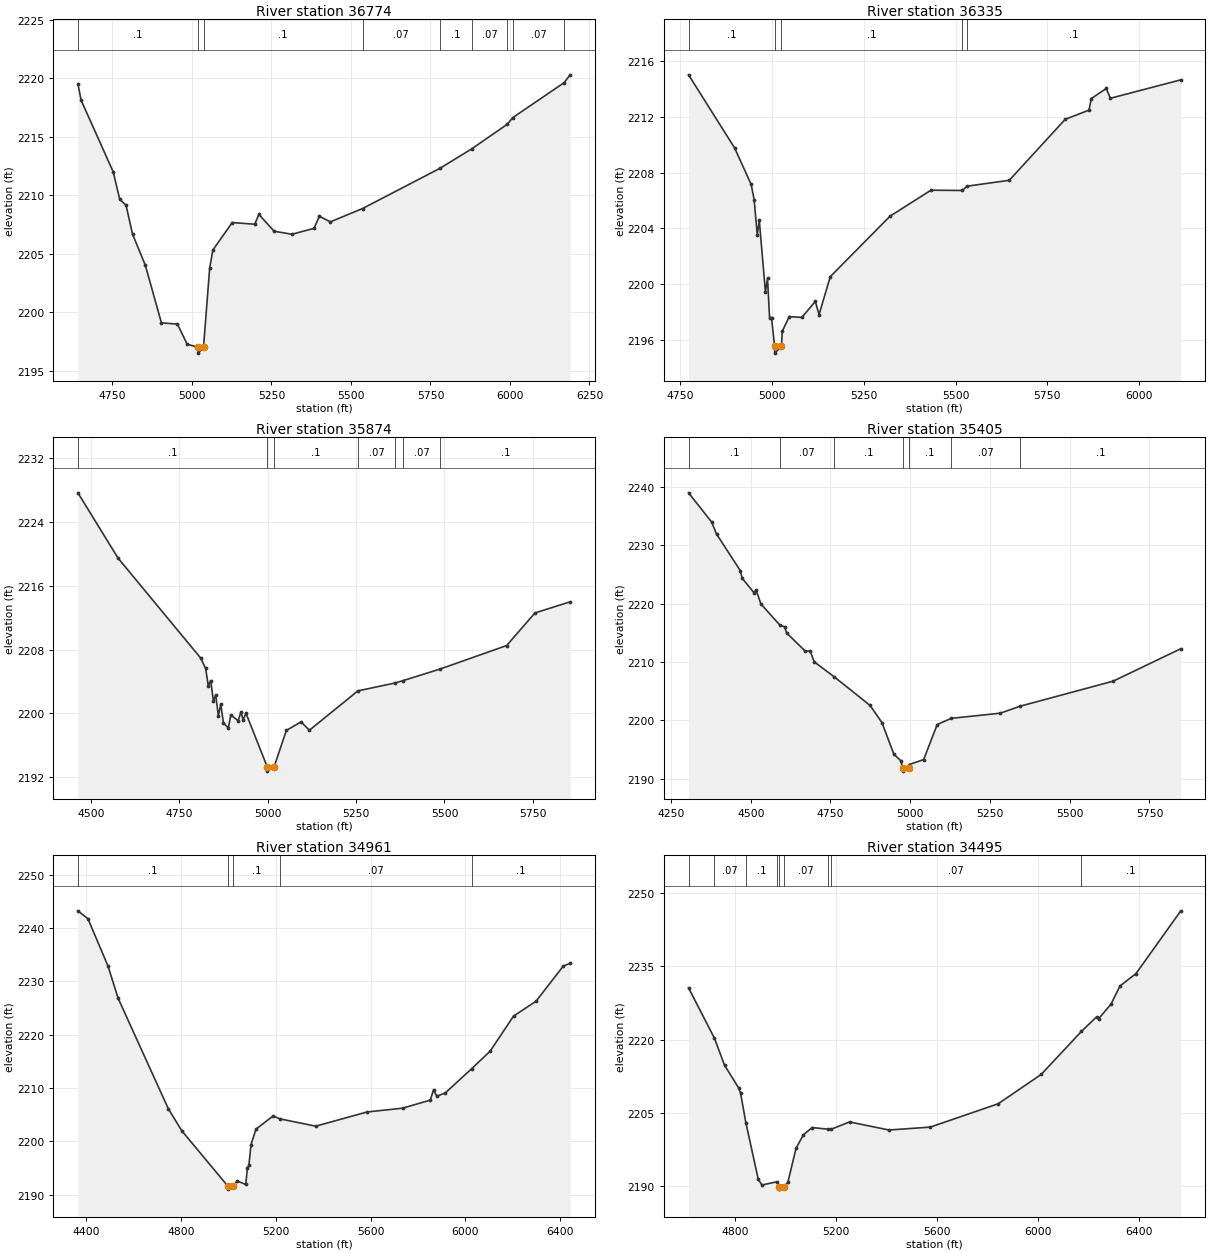
Type RM Length L Ch R = 1,36774,439,439,439
BEGIN DESCRIPTION:
Stream0095 66.0
END DESCRIPTION:
XS GIS Cut Line= 4
      1773775.00     13905525.00      1774125.00     13905575.00
      1774441.06     13905522.32      1774809.92     13904729.94
#Sta/Elev= 30
  4641.3 2219.52  4651.4 2218.12  4752.4 2211.99  4772.6 2209.67  4792.8 2209.13
  4813.0 2206.68  4853.4 2204.01  4903.9 2199.09  4954.4 2198.98  4984.7 2197.27
  5019.3 2197.00  5019.8 2196.50  5036.3 2197.00  5055.7 2203.77  5065.8 2205.32
  5126.6 2207.66  5197.6 2207.52  5210.3 2208.36  5258.4 2206.92  5314.7 2206.66
  5383.9 2207.17  5400.6 2208.20  5435.2 2207.72  5536.3 2208.86  5780.1 2212.30
  5880.7 2213.98  5991.9 2216.07  6008.7 2216.63  6170.4 2219.62  6189.3 2220.29
#Mann=9,-1,0
  4641.3     0.1       0  5019.3    0.05       0  5036.3     0.1       0
  5536.3    0.07       0  5780.1     0.1       0  5880.7    0.07       0
  5991.9     0.1       0  6008.7    0.07       0  6170.4     0.1       0
Bank Sta=5019.3,5036.3
Exp/Cntr=0.3,0.1

Type RM Length L Ch R = 1,36335,461,461,461
BEGIN DESCRIPTION:
Stream0095 65.0
END DESCRIPTION:
XS GIS Cut Line= 3
      1773825.04     13905875.02      1774025.00     13905975.00
      1775125.00     13905775.00
#Sta/Elev= 30
  4772.3 2215.01  4898.0 2209.76  4942.8 2207.16  4951.1 2206.06  4959.5 2203.54
  4965.1 2204.57  4981.9 2199.43  4987.5 2200.42  4993.1 2197.61  4998.4 2197.61
  5006.7 2195.56  5007.2 2195.06  5025.6 2195.56  5027.6 2196.62  5046.7 2197.68
  5081.0 2197.62  5117.8 2198.77  5128.0 2197.82  5158.5 2200.54  5321.1 2204.87
  5432.9 2206.74  5518.3 2206.72  5531.9 2207.03  5646.4 2207.45  5798.8 2211.82
  5863.6 2212.48  5870.0 2213.31  5910.6 2214.03  5922.1 2213.33  6113.9 2214.65
#Mann=5,-1,0
  4772.3     0.1       0  5006.7    0.05       0  5025.6     0.1       0
  5518.3    0.07       0  5531.9     0.1       0
Bank Sta=5006.7,5025.6
Exp/Cntr=0.3,0.1

Type RM Length L Ch R = 1,35874,469,469,469
BEGIN DESCRIPTION:
Stream0095 64.0
END DESCRIPTION:
XS GIS Cut Line= 3
      1773825.01     13906774.99      1774175.00     13906375.00
      1774874.98     13905875.01
#Sta/Elev= 30
  4463.6 2227.62  4577.0 2219.45  4810.5 2206.94  4824.7 2205.63  4832.3 2203.45
  4839.0 2204.11  4846.6 2201.60  4853.2 2202.26  4860.8 2199.71  4867.4 2201.16
  4875.0 2198.84  4888.8 2198.16  4895.9 2199.80  4916.8 2199.08  4924.4 2200.17
  4931.0 2199.16  4938.6 2200.05  4999.1 2193.27  4999.6 2192.77  5018.1 2193.27
  5052.8 2197.86  5094.6 2198.94  5118.0 2197.89  5255.3 2202.82  5359.6 2203.80
  5381.9 2204.09  5488.6 2205.57  5675.9 2208.50  5755.8 2212.58  5855.3 2213.97
#Mann=7,-1,0
  4463.6     0.1       0  4999.1    0.05       0  5018.1     0.1       0
  5255.3    0.07       0  5359.6     0.1       0  5381.9    0.07       0
  5488.6     0.1       0
Bank Sta=4999.1,5018.1
Exp/Cntr=0.3,0.1

Type RM Length L Ch R = 1,35405,444,444,444
BEGIN DESCRIPTION:
Stream0095 63.0
END DESCRIPTION:
XS GIS Cut Line= 3
      1773875.03     13907074.98      1774475.00     13906725.00
      1775074.99     13906125.01
#Sta/Elev= 30
  4305.2 2238.98  4377.5 2233.98  4393.2 2231.89  4467.2 2225.66  4473.4 2224.33
  4510.7 2221.83  4516.4 2222.38  4532.2 2219.92  4592.1 2216.27  4606.2 2216.04
  4612.4 2214.98  4671.1 2211.84  4686.8 2211.86  4698.8 2210.03  4762.2 2207.43
  4874.5 2202.53  4911.7 2199.57  4948.9 2194.17  4970.4 2193.07  4976.6 2191.78
  4977.1 2191.28  4995.7 2191.78  4996.9 2192.41  5042.2 2193.26  5084.6 2199.26
  5128.8 2200.33  5282.6 2201.21  5344.0 2202.40  5636.2 2206.70  5848.3 2212.26
#Mann=7,-1,0
  4305.2     0.1       0  4592.1    0.07       0  4762.2     0.1       0
  4976.6    0.05       0  4995.7     0.1       0  5128.8    0.07       0
  5344.0     0.1       0
Bank Sta=4976.6,4995.7
Exp/Cntr=0.3,0.1

Type RM Length L Ch R = 1,34961,466,466,466
BEGIN DESCRIPTION:
Stream0095 62.0
END DESCRIPTION:
XS GIS Cut Line= 3
      1774274.99     13907525.01      1774725.00     13907075.00
      1775924.98     13906275.01
#Sta/Elev= 30
  4363.8 2243.25  4406.2 2241.77  4491.1 2232.87  4533.5 2226.86  4745.6 2206.13
  4802.2 2202.01  4998.1 2191.55  4998.6 2191.05  5017.3 2191.55  5036.3 2192.59
  5072.3 2191.93  5079.8 2194.98  5085.8 2195.52  5094.9 2199.41  5115.9 2202.31
  5188.0 2204.77  5217.8 2204.22  5368.3 2202.86  5584.6 2205.52  5734.8 2206.23
  5852.0 2207.75  5865.5 2209.69  5879.1 2208.47  5915.1 2209.09  6026.3 2213.63
  6104.4 2216.92  6203.6 2223.51  6298.2 2226.29  6413.9 2232.91  6442.4 2233.39
#Mann=5,-1,0
  4363.8     0.1       0  4998.1    0.05       0  5017.3     0.1       0
  5217.8    0.07       0  6026.3     0.1       0
Bank Sta=4998.1,5017.3
Exp/Cntr=0.3,0.1

Type RM Length L Ch R = 1,34495,473,473,473
BEGIN DESCRIPTION:
Stream0095 61.0
END DESCRIPTION:
XS GIS Cut Line= 3
      1774724.98     13907725.02      1774975.00     13907425.00
      1776175.01     13906425.00
#Sta/Elev= 30
  4614.2 2230.57  4717.0 2220.27  4756.8 2214.78  4812.7 2210.14  4820.6 2209.03
  4841.6 2202.99  4890.8 2191.43  4905.2 2190.29  4966.3 2190.97  4973.6 2189.95
  4974.1 2189.45  4992.9 2189.95  5008.0 2190.82  5040.5 2197.79  5069.2 2200.52
  5104.3 2202.03  5165.5 2201.71  5179.3 2201.67  5252.7 2203.18  5408.9 2201.53
  5572.9 2202.12  5842.4 2206.89  6012.9 2212.88  6172.5 2221.67  6232.9 2224.65
  6240.7 2224.26  6290.2 2227.26  6325.3 2230.95  6389.1 2233.49  6566.8 2246.31
#Mann=9,-1,0
  4614.2     0.1       0  4717.0    0.07       0  4841.6     0.1       0
  4966.3    0.07       0  4973.6    0.05       0  4992.9    0.07       0
  5165.5     0.1       0  5179.3    0.07       0  6172.5     0.1       0
Bank Sta=4973.6,4992.9
Exp/Cntr=0.3,0.1

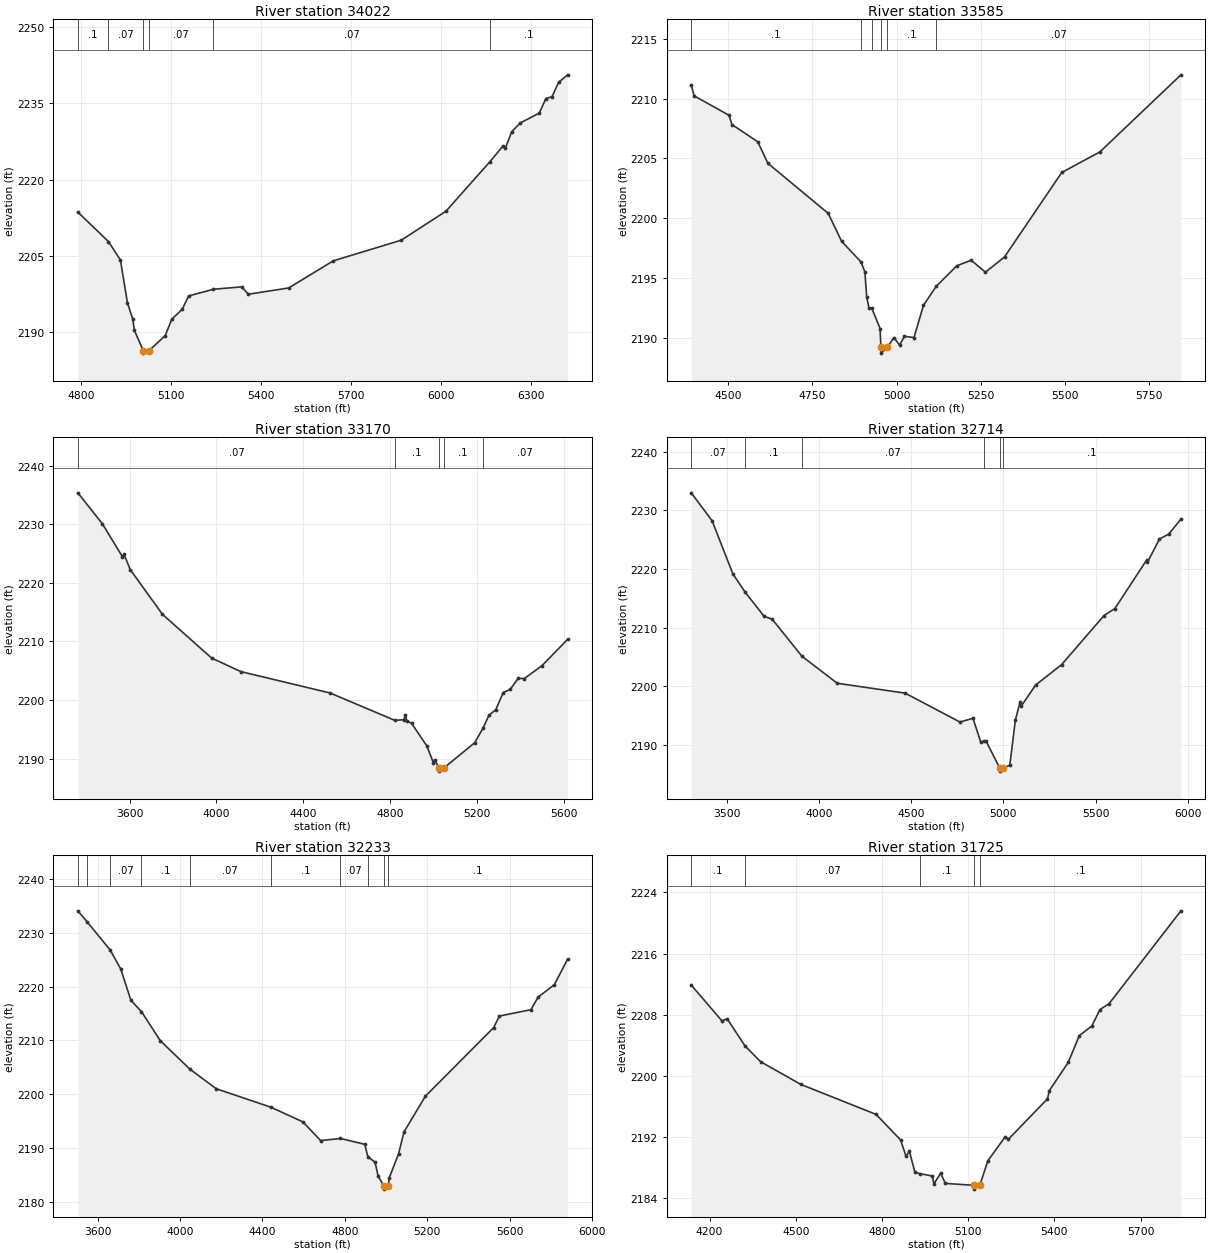
Type RM Length L Ch R = 1,34022,437,437,437
BEGIN DESCRIPTION:
Stream0095 60.0
END DESCRIPTION:
XS GIS Cut Line= 3
      1775025.00     13907825.00      1775225.00     13907775.00
      1776285.49     13906822.64
#Sta/Elev= 30
  4789.8 2213.62  4891.7 2207.83  4931.5 2204.18  4954.7 2195.84  4972.8 2192.53
  4977.9 2190.37  5007.6 2186.40  5008.1 2185.90  5026.9 2186.40  5080.8 2189.34
  5102.5 2192.57  5137.6 2194.54  5158.5 2197.14  5241.5 2198.46  5335.7 2198.93
  5357.4 2197.48  5491.9 2198.71  5640.7 2204.05  5867.2 2208.11  6015.9 2213.80
  6161.2 2223.46  6206.5 2226.66  6214.0 2226.19  6234.9 2229.43  6263.4 2231.15
  6326.9 2233.10  6348.6 2235.93  6369.5 2236.34  6391.2 2239.14  6421.3 2240.62
#Mann=6,-1,0
  4789.8     0.1       0  4891.7    0.07       0  5007.6    0.05       0
  5026.9    0.07       0  5241.5    0.07       0  6161.2     0.1       0
Bank Sta=5007.6,5026.9
Exp/Cntr=0.3,0.1

Type RM Length L Ch R = 1,33585,415,415,415
BEGIN DESCRIPTION:
Stream0095 59.0
END DESCRIPTION:
XS GIS Cut Line= 3
      1775024.97     13908175.02      1775575.00     13907925.00
      1776174.99     13907325.01
#Sta/Elev= 30
  4390.8 2211.14  4399.6 2210.23  4502.9 2208.61  4511.7 2207.83  4588.6 2206.38
  4618.2 2204.59  4797.3 2200.40  4836.8 2198.07  4894.8 2196.33  4906.0 2195.50
  4911.5 2193.38  4918.1 2192.49  4926.4 2192.47  4951.1 2190.77  4953.5 2189.21
  4954.0 2188.71  4972.8 2189.21  4992.2 2190.01  5009.1 2189.38  5023.3 2190.12
  5051.6 2190.01  5079.8 2192.71  5117.4 2194.29  5178.8 2196.02  5221.3 2196.48
  5263.7 2195.48  5320.3 2196.76  5490.0 2203.82  5603.1 2205.54  5843.5 2211.99
#Mann=6,-1,0
  4390.8     0.1       0  4894.8    0.07       0  4926.4     0.1       0
  4953.5    0.05       0  4972.8     0.1       0  5117.4    0.07       0
Bank Sta=4953.5,4972.8
Exp/Cntr=0.3,0.1

Type RM Length L Ch R = 1,33170,456,456,456
BEGIN DESCRIPTION:
Stream0095 58.0
END DESCRIPTION:
XS GIS Cut Line= 3
      1774825.01     13909224.99      1775925.00     13908025.00
      1776225.02     13907474.97
#Sta/Elev= 30
  3362.1 2235.37  3475.2 2230.06  3567.1 2224.46  3574.5 2224.86  3602.9 2222.27
  3751.5 2214.62  3977.8 2207.16  4112.2 2204.85  4522.9 2201.20  4820.8 2196.53
  4862.6 2196.63  4869.4 2197.40  4876.8 2196.40  4897.8 2196.04  4968.7 2192.14
  4998.0 2189.32  5003.7 2189.80  5025.6 2188.36  5026.1 2187.86  5045.4 2188.36
  5188.8 2192.71  5226.2 2195.14  5254.3 2197.39  5286.1 2198.37  5320.3 2201.28
  5352.1 2201.81  5388.6 2203.69  5417.6 2203.67  5499.2 2205.89  5616.5 2210.36
#Mann=5,-1,0
  3362.1    0.07       0  4820.8     0.1       0  5025.6    0.05       0
  5045.4     0.1       0  5226.2    0.07       0
Bank Sta=5025.6,5045.4
Exp/Cntr=0.3,0.1

Type RM Length L Ch R = 1,32714,481,481,481
BEGIN DESCRIPTION:
Stream0095 57.0
END DESCRIPTION:
XS GIS Cut Line= 3
      1775075.03     13909374.97      1776275.00     13908175.00
      1777231.07     13908119.46
#Sta/Elev= 30
  3307.5 2233.00  3420.6 2228.25  3533.7 2219.15  3600.1 2216.04  3703.4 2211.91
  3745.9 2211.46  3908.0 2205.11  4099.4 2200.50  4467.1 2198.82  4764.1 2193.89
  4834.8 2194.52  4877.2 2190.47  4893.0 2190.61  4905.5 2190.66  4980.4 2186.01
  4980.9 2185.51  5000.3 2186.01  5034.6 2186.53  5064.6 2194.18  5090.2 2197.33
  5095.2 2196.54  5174.8 2200.21  5315.0 2203.67  5545.4 2212.06  5604.3 2213.26
  5775.7 2221.50  5780.7 2221.14  5845.9 2225.12  5896.0 2225.96  5962.2 2228.50
#Mann=6,-1,0
  3307.5    0.07       0  3600.1     0.1       0  3908.0    0.07       0
  4893.0     0.1       0  4980.4    0.05       0  5000.3     0.1       0
Bank Sta=4980.4,5000.3
Exp/Cntr=0.3,0.1

Type RM Length L Ch R = 1,32233,508,508,508
BEGIN DESCRIPTION:
Stream0095 56.0
END DESCRIPTION:
XS GIS Cut Line= 3
      1775175.00     13909525.00      1776375.00     13908625.00
      1777220.99     13908392.70
#Sta/Elev= 30
  3504.3 2234.08  3550.3 2231.98  3659.9 2226.84  3711.6 2223.32  3761.6 2217.44
  3812.8 2215.33  3904.3 2209.92  4047.9 2204.63  4176.2 2200.98  4439.6 2197.57
  4597.0 2194.81  4682.4 2191.34  4778.3 2191.73  4897.0 2190.65  4911.8 2188.35
  4947.0 2187.30  4961.6 2184.74  4991.2 2182.81  4991.7 2182.31  5011.2 2182.81
  5014.7 2184.31  5061.1 2188.92  5087.3 2192.96  5191.0 2199.59  5522.8 2212.37
  5550.3 2214.51  5703.6 2215.69  5738.1 2218.02  5817.3 2220.35  5881.6 2225.11
#Mann=10,-1,0
  3504.3    0.07       0  3550.3     0.1       0  3659.9    0.07       0
  3812.8     0.1       0  4047.9    0.07       0  4439.6     0.1       0
  4778.3    0.07       0  4911.8     0.1       0  4991.2    0.05       0
  5011.2     0.1       0
Bank Sta=4991.2,5011.2
Exp/Cntr=0.3,0.1

Type RM Length L Ch R = 1,31725,540,540,540
BEGIN DESCRIPTION:
Stream0095 55.0
END DESCRIPTION:
XS GIS Cut Line= 3
      1775524.97     13909375.01      1776325.00     13909075.00
      1777074.97     13908675.01
#Sta/Elev= 30
  4136.1 2211.87  4242.9 2207.19  4261.6 2207.44  4323.1 2203.91  4377.3 2201.84
  4517.9 2198.85  4779.6 2194.93  4865.0 2191.57  4883.7 2189.44  4895.3 2190.12
  4914.9 2187.34  4933.0 2187.16  4975.4 2186.86  4980.7 2185.83  5004.3 2187.22
  5020.6 2185.89  5120.4 2185.64  5120.9 2185.14  5140.4 2185.64  5168.7 2188.86
  5228.5 2191.97  5240.2 2191.68  5375.9 2196.96  5382.6 2198.05  5448.5 2201.75
  5486.7 2205.24  5530.6 2206.51  5558.3 2208.64  5590.8 2209.45  5840.5 2221.59
#Mann=5,-1,0
  4136.1     0.1       0  4323.1    0.07       0  4933.0     0.1       0
  5120.4    0.05       0  5140.4     0.1       0
Bank Sta=5120.4,5140.4
Exp/Cntr=0.3,0.1

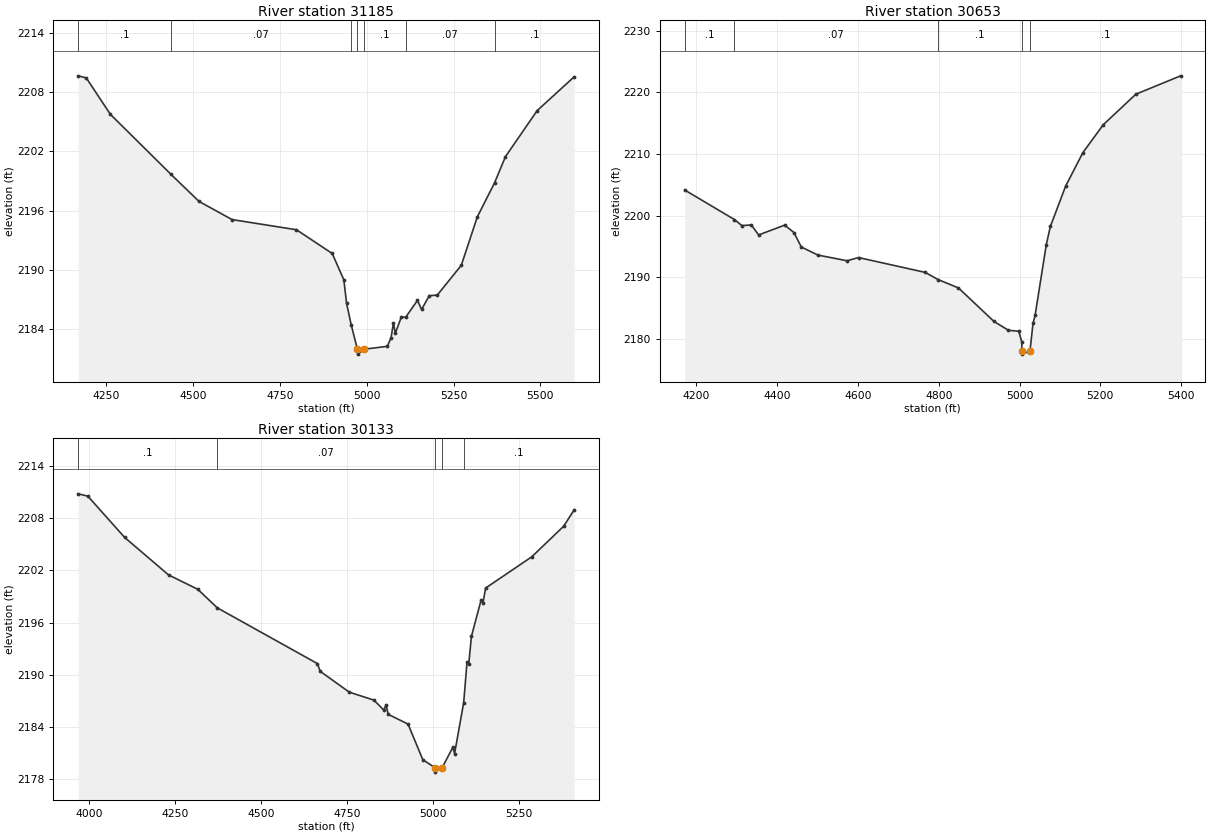
Type RM Length L Ch R = 1,31185,532,532,532
BEGIN DESCRIPTION:
Stream0095 54.0
END DESCRIPTION:
XS GIS Cut Line= 3
      1775675.00     13909725.00      1776475.00     13909525.00
      1777025.03     13909775.01
#Sta/Elev= 30
  4168.8 2209.64  4192.0 2209.43  4261.6 2205.74  4435.9 2199.68  4516.7 2196.94
  4612.0 2195.10  4797.6 2194.07  4900.6 2191.67  4934.1 2189.00  4941.9 2186.64
  4955.3 2184.45  4973.1 2181.99  4973.6 2181.49  4993.2 2181.99  5059.3 2182.28
  5070.3 2183.17  5076.9 2184.64  5082.4 2183.60  5100.0 2185.27  5112.0 2185.21
  5146.1 2186.92  5158.2 2186.01  5180.2 2187.40  5203.2 2187.46  5272.4 2190.47
  5318.6 2195.37  5368.2 2198.81  5399.8 2201.47  5491.0 2206.12  5597.6 2209.54
#Mann=7,-1,0
  4168.8     0.1       0  4435.9    0.07       0  4955.3     0.1       0
  4973.1    0.05       0  4993.2     0.1       0  5112.0    0.07       0
  5368.2     0.1       0
Bank Sta=4973.1,4993.2
Exp/Cntr=0.3,0.1

Type RM Length L Ch R = 1,30653,520,520,520
BEGIN DESCRIPTION:
Stream0095 53.0
END DESCRIPTION:
XS GIS Cut Line= 3
      1775824.97     13909774.99      1776625.00     13909975.00
      1777025.03     13910025.00
#Sta/Elev= 30
  4170.9 2204.17  4294.2 2199.38  4312.7 2198.40  4335.9 2198.52  4353.9 2196.89
  4418.3 2198.48  4441.5 2197.28  4459.6 2194.94  4500.8 2193.63  4572.9 2192.71
  4601.3 2193.23  4766.2 2190.83  4798.1 2189.67  4848.7 2188.31  4936.3 2182.90
  4972.4 2181.45  4998.1 2181.30  5005.6 2179.51  5005.7 2178.09  5006.2 2177.59
  5025.8 2178.09  5033.3 2182.59  5038.4 2183.85  5066.1 2195.30  5076.2 2198.26
  5114.0 2204.79  5156.8 2210.23  5207.2 2214.74  5287.8 2219.68  5398.7 2222.66
#Mann=5,-1,0
  4170.9     0.1       0  4294.2    0.07       0  4798.1     0.1       0
  5005.7    0.05       0  5025.8     0.1       0
Bank Sta=5005.7,5025.8
Exp/Cntr=0.3,0.1

Type RM Length L Ch R = 1,30133,553,553,553
BEGIN DESCRIPTION:
Stream0095 52.0
END DESCRIPTION:
XS GIS Cut Line= 3
      1775624.97     13909774.98      1776425.00     13910425.00
      1776824.98     13910325.01
#Sta/Elev= 30
  3968.7 2210.81  3996.7 2210.54  4103.8 2205.80  4231.6 2201.49  4316.6 2199.84
  4373.3 2197.71  4664.8 2191.30  4672.7 2190.42  4757.4 2188.02  4829.3 2187.10
  4857.8 2185.96  4864.5 2186.57  4870.9 2185.47  4928.4 2184.35  4971.5 2180.25
  5007.5 2179.33  5008.0 2178.83  5027.6 2179.33  5058.8 2181.68  5063.9 2180.97
  5090.4 2186.82  5100.0 2191.45  5105.2 2191.29  5112.9 2194.43  5141.2 2198.63
  5146.4 2198.24  5154.1 2199.98  5288.1 2203.56  5380.9 2207.07  5411.8 2208.96
#Mann=5,-1,0
  3968.7     0.1       0  4373.3    0.07       0  5007.5    0.05       0
  5027.6    0.07       0  5090.4     0.1       0
Bank Sta=5007.5,5027.6
Exp/Cntr=0.3,0.1