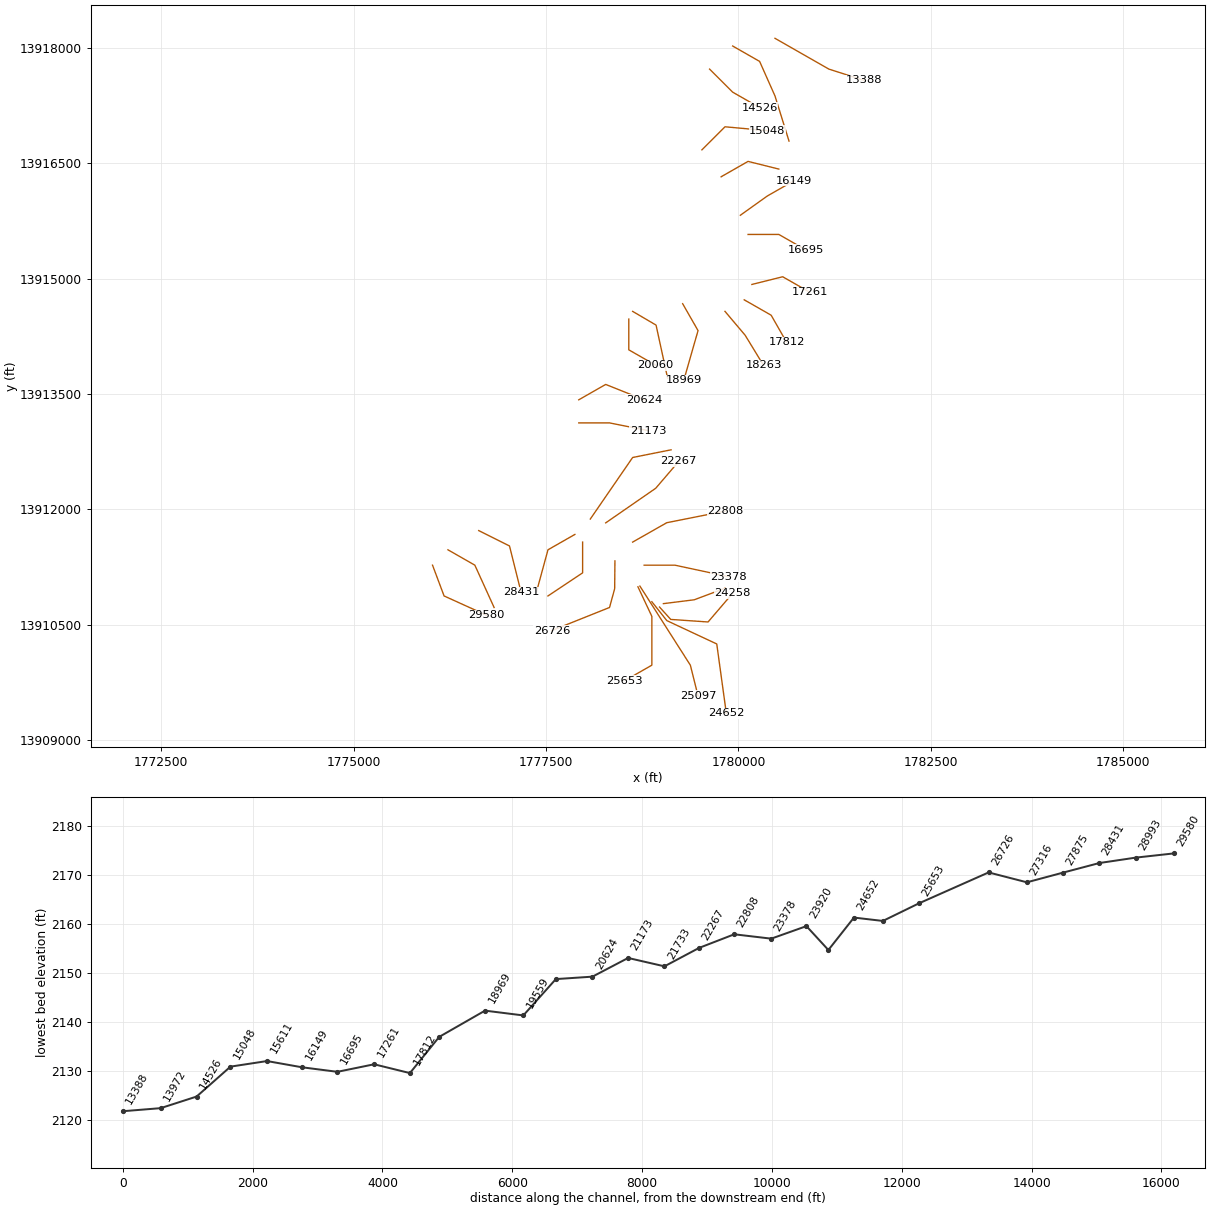
HEC-RAS study Stream0095.prj: Stream0095 Base Level Engineering

--- Stream0095.g01 (geometry) --- (continued)

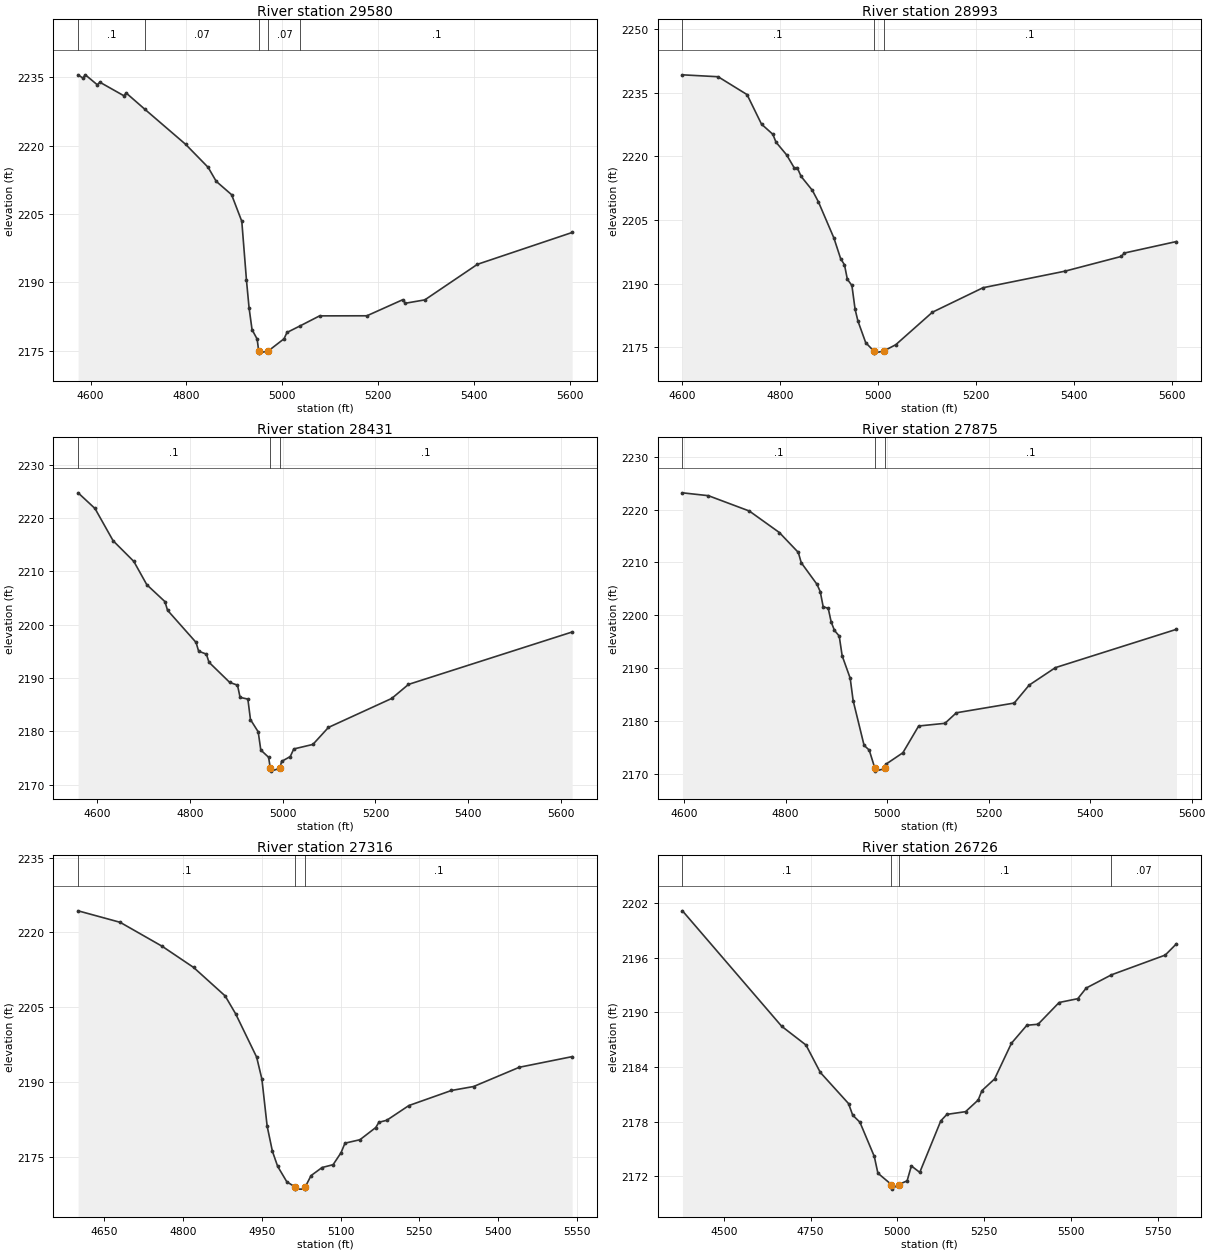
Type RM Length L Ch R = 1,29580,587,587,587
BEGIN DESCRIPTION:
Stream0095 51.0
END DESCRIPTION:
XS GIS Cut Line= 3
      1776025.01     13911274.97      1776175.00     13910875.00
      1776724.98     13910625.01
#Sta/Elev= 30
  4574.1 2235.50  4583.9 2234.82  4589.2 2235.52  4614.1 2233.34  4619.5 2233.90
  4669.3 2230.95  4674.6 2231.52  4712.7 2228.03  4798.4 2220.29  4845.5 2215.23
  4862.4 2212.16  4894.5 2209.23  4915.8 2203.39  4925.6 2190.41  4931.0 2184.40
  4937.2 2179.63  4947.9 2177.55  4951.0 2174.98  4951.5 2174.48  4971.4 2174.98
  5004.0 2177.63  5010.1 2179.01  5038.2 2180.49  5078.2 2182.65  5177.0 2182.67
  5251.7 2186.19  5257.2 2185.42  5297.9 2186.16  5407.7 2193.96  5605.4 2200.94
#Mann=5,-1,0
  4574.1     0.1       0  4712.7    0.07       0  4951.0    0.05       0
  4971.4    0.07       0  5038.2     0.1       0
Bank Sta=4951,4971.4
Exp/Cntr=0.3,0.1

Type RM Length L Ch R = 1,28993,562,562,562
BEGIN DESCRIPTION:
Stream0095 50.0
END DESCRIPTION:
XS GIS Cut Line= 3
      1776225.01     13911475.00      1776575.00     13911275.00
      1776825.02     13910724.96
#Sta/Elev= 30
  4601.3 2239.23  4674.0 2238.78  4733.0 2234.57  4762.5 2227.60  4785.6 2225.21
  4792.0 2223.36  4813.6 2220.37  4829.5 2217.24  4835.2 2217.36  4843.2 2215.29
  4866.2 2211.99  4878.4 2209.31  4910.1 2200.76  4923.8 2195.91  4931.7 2194.43
  4937.5 2191.04  4946.8 2189.57  4953.3 2183.96  4959.1 2181.19  4974.9 2176.10
  4991.3 2174.12  4991.8 2173.62  5011.7 2174.12  5036.3 2175.61  5111.0 2183.27
  5214.2 2189.04  5381.2 2192.94  5496.5 2196.43  5502.0 2197.21  5608.6 2199.93
#Mann=3,-1,0
  4601.3     0.1       0  4991.3    0.05       0  5011.7     0.1       0
Bank Sta=4991.3,5011.7
Exp/Cntr=0.3,0.1

Type RM Length L Ch R = 1,28431,556,556,556
BEGIN DESCRIPTION:
Stream0095 49.0
END DESCRIPTION:
XS GIS Cut Line= 3
      1776624.97     13911725.01      1777025.00     13911525.00
      1777175.00     13910925.01
#Sta/Elev= 30
  4558.6 2224.72  4595.0 2221.78  4634.1 2215.73  4678.8 2211.85  4706.8 2207.48
  4745.9 2204.31  4751.5 2202.69  4813.0 2196.66  4818.6 2195.01  4835.3 2194.46
  4840.9 2192.94  4885.7 2189.15  4902.4 2188.64  4908.0 2186.35  4924.8 2186.02
  4930.4 2182.18  4947.1 2179.88  4952.7 2176.47  4969.5 2175.11  4973.3 2173.01
  4973.8 2172.51  4993.7 2173.01  4997.5 2174.33  5016.2 2175.24  5023.9 2176.67
  5065.1 2177.52  5098.6 2180.71  5235.2 2186.15  5271.3 2188.78  5624.3 2198.61
#Mann=3,-1,0
  4558.6     0.1       0  4973.3    0.05       0  4993.7     0.1       0
Bank Sta=4973.3,4993.7
Exp/Cntr=0.3,0.1

Type RM Length L Ch R = 1,27875,559,559,559
BEGIN DESCRIPTION:
Stream0095 48.0
END DESCRIPTION:
XS GIS Cut Line= 3
      1777875.01     13911675.01      1777525.00     13911475.00
      1777375.00     13910925.01
#Sta/Elev= 30
  4596.9 2223.17  4648.0 2222.63  4728.6 2219.73  4787.7 2215.67  4825.1 2211.91
  4830.9 2209.96  4861.8 2205.89  4868.3 2204.51  4874.1 2201.64  4884.1 2201.33
  4889.9 2198.75  4896.4 2197.15  4905.7 2196.10  4911.5 2192.37  4927.3 2188.13
  4933.1 2183.91  4954.7 2175.43  4964.8 2174.54  4976.1 2171.06  4976.6 2170.56
  4996.5 2171.06  4997.1 2171.83  5031.1 2174.03  5062.2 2179.09  5114.0 2179.60
  5136.5 2181.59  5250.5 2183.43  5279.9 2186.82  5331.7 2190.13  5570.1 2197.37
#Mann=3,-1,0
  4596.9     0.1       0  4976.1    0.05       0  4996.5     0.1       0
Bank Sta=4976.1,4996.5
Exp/Cntr=0.3,0.1

Type RM Length L Ch R = 1,27316,590,590,590
BEGIN DESCRIPTION:
Stream0095 47.0
END DESCRIPTION:
XS GIS Cut Line= 3
      1777975.00     13911575.01      1777975.00     13911175.00
      1777525.04     13910875.02
#Sta/Elev= 30
  4600.3 2224.34  4680.3 2222.04  4760.3 2217.24  4820.3 2212.99  4880.3 2207.29
  4900.3 2203.70  4940.3 2195.02  4950.3 2190.61  4960.3 2181.19  4970.3 2176.16
  4980.3 2173.14  4997.8 2170.03  5012.6 2169.07  5013.1 2168.57  5032.6 2168.57
  5033.1 2169.07  5043.9 2171.28  5064.9 2172.90  5085.9 2173.47  5101.0 2175.87
  5108.5 2177.78  5137.0 2178.47  5167.1 2180.91  5173.1 2181.96  5188.1 2182.37
  5230.2 2185.32  5311.3 2188.34  5353.4 2189.13  5440.5 2192.99  5541.1 2195.12
#Mann=3,-1,0
  4600.3     0.1       0  5012.6    0.05       0  5033.1     0.1       0
Bank Sta=5012.6,5033.1
Exp/Cntr=0.3,0.1

Type RM Length L Ch R = 1,26726,1073,1073,1073
BEGIN DESCRIPTION:
Stream0095 46.0
END DESCRIPTION:
XS GIS Cut Line= 4
      1778395.03     13911330.60      1778391.54     13910968.98
      1778325.00     13910725.00      1777575.00     13910425.00
#Sta/Elev= 30
  4381.3 2201.16  4666.9 2188.48  4736.9 2186.42  4778.2 2183.41  4859.4 2179.99
  4871.4 2178.72  4892.2 2177.94  4933.6 2174.18  4944.0 2172.34  4983.0 2171.09
  4983.5 2170.59  5003.5 2171.09  5028.1 2171.50  5040.3 2173.14  5064.5 2172.43
  5125.1 2178.09  5142.6 2178.80  5196.4 2179.10  5232.8 2180.38  5243.5 2181.41
  5279.9 2182.69  5328.4 2186.61  5372.8 2188.59  5405.1 2188.70  5465.7 2191.09
  5519.5 2191.51  5543.8 2192.68  5616.4 2194.13  5771.3 2196.30  5803.6 2197.54
#Mann=4,-1,0
  4381.3     0.1       0  4983.0    0.05       0  5003.5     0.1       0
  5616.4    0.07       0
Bank Sta=4983,5003.5
Exp/Cntr=0.3,0.1

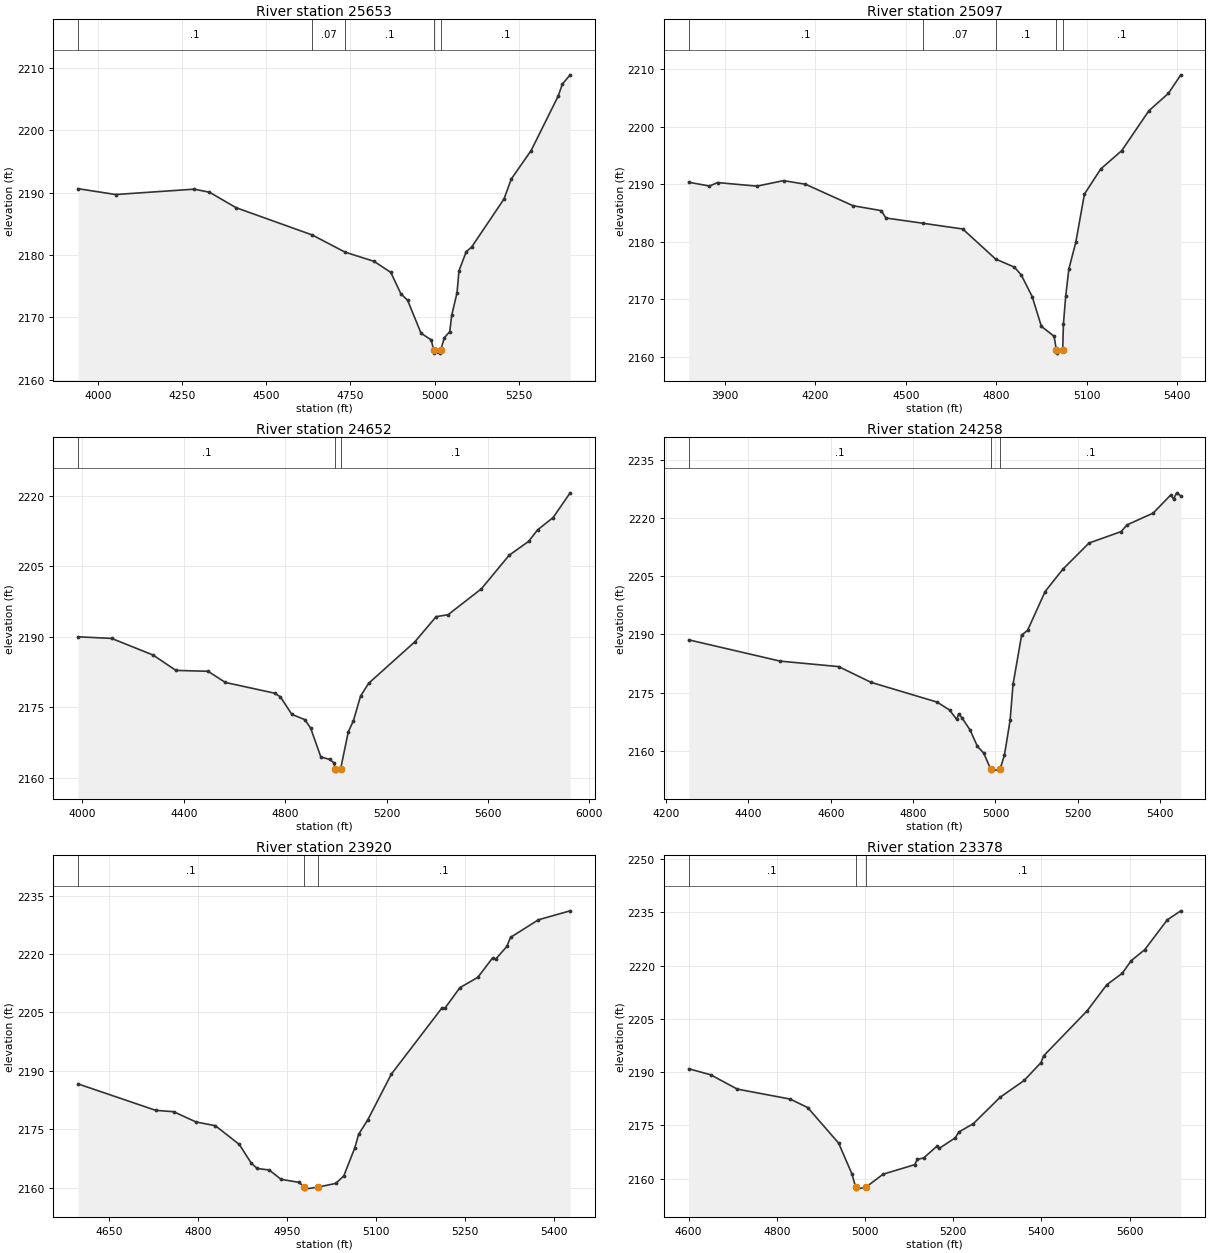
Type RM Length L Ch R = 1,25653,556,556,556
BEGIN DESCRIPTION:
Stream0095 45.0
END DESCRIPTION:
XS GIS Cut Line= 4
      1778693.75     13910994.10      1778875.00     13910609.34
      1778875.00     13909975.00      1778524.97     13909774.98
#Sta/Elev= 30
  3940.3 2190.65  4052.1 2189.71  4285.5 2190.57  4331.1 2190.08  4410.0 2187.60
  4636.1 2183.23  4734.4 2180.46  4820.0 2179.00  4870.0 2177.22  4900.0 2173.79
  4920.0 2172.75  4960.0 2167.46  4990.0 2166.40  4997.6 2164.77  4998.1 2164.27
  5017.7 2164.27  5018.2 2164.77  5029.5 2166.76  5045.3 2167.72  5051.1 2170.34
  5066.9 2173.96  5072.7 2177.48  5094.3 2180.55  5110.1 2181.27  5206.6 2189.00
  5228.1 2192.20  5287.2 2196.77  5367.8 2205.53  5380.0 2207.42  5403.1 2208.91
#Mann=5,-1,0
  3940.3     0.1       0  4636.1    0.07       0  4734.4     0.1       0
  4997.6    0.05       0  5018.2     0.1       0
Bank Sta=4997.6,5018.2
Exp/Cntr=0.3,0.1

Type RM Length L Ch R = 1,25097,445,445,445
BEGIN DESCRIPTION:
Stream0095 44.0
END DESCRIPTION:
XS GIS Cut Line= 3
      1778719.71     13911002.92      1779375.00     13909975.00
      1779474.99     13909575.03
#Sta/Elev= 30
  3780.6 2190.39  3849.3 2189.73  3876.5 2190.33  4006.9 2189.71  4094.9 2190.67
  4167.7 2190.04  4325.1 2186.31  4419.0 2185.45  4434.3 2184.17  4557.8 2183.25
  4689.0 2182.26  4798.1 2177.03  4860.1 2175.63  4882.8 2174.28  4919.2 2170.51
  4949.7 2165.33  4992.0 2163.59  4999.5 2161.17  5000.0 2160.67  5020.3 2161.17
  5022.8 2165.77  5030.5 2170.67  5040.9 2175.32  5064.0 2180.00  5092.4 2188.33
  5146.5 2192.70  5216.1 2195.89  5306.3 2202.84  5370.7 2205.84  5411.9 2209.07
#Mann=5,-1,0
  3780.6     0.1       0  4557.8    0.07       0  4798.1     0.1       0
  4999.5    0.05       0  5020.3     0.1       0
Bank Sta=4999.5,5020.3
Exp/Cntr=0.3,0.1

Type RM Length L Ch R = 1,24652,394,394,394
BEGIN DESCRIPTION:
Stream0095 43.0
END DESCRIPTION:
XS GIS Cut Line= 4
      1778874.63     13910800.07      1779069.04     13910554.39
      1779718.11     13910250.69      1779842.31     13909348.19
#Sta/Elev= 30
  3983.1 2189.99  4115.7 2189.65  4279.2 2186.10  4369.2 2182.83  4495.9 2182.64
  4564.4 2180.26  4758.1 2177.98  4781.0 2177.21  4826.6 2173.45  4877.8 2172.33
  4900.7 2170.52  4940.8 2164.38  4976.4 2163.84  4992.0 2163.14  4998.1 2161.86
  4998.6 2161.36  5018.9 2161.86  5049.0 2169.73  5069.2 2172.08  5097.3 2177.34
  5129.8 2180.11  5311.5 2188.92  5395.5 2194.28  5442.7 2194.70  5573.9 2200.22
  5683.5 2207.38  5760.5 2210.34  5796.0 2212.81  5856.6 2215.39  5924.0 2220.68
#Mann=3,-1,0
  3983.1     0.1       0  4998.1    0.05       0  5018.9     0.1       0
Bank Sta=4998.1,5018.9
Exp/Cntr=0.3,0.1

Type RM Length L Ch R = 1,24258,338,338,338
BEGIN DESCRIPTION:
Mapping XS 5bc4179a
END DESCRIPTION:
XS GIS Cut Line= 4
      1778974.45     13910730.92      1779119.98     13910569.82
      1779604.99     13910536.53      1779924.47     13910909.83
#Sta/Elev= 30
  4255.3 2188.58  4477.4 2183.09  4619.3 2181.68  4698.0 2177.62  4858.3 2172.53
  4888.4 2170.49  4905.7 2168.08  4910.7 2169.49  4918.5 2168.50  4938.5 2165.31
  4956.1 2161.12  4971.3 2159.40  4988.6 2155.23  4989.1 2154.73  5011.1 2155.23
  5021.8 2158.88  5035.5 2167.84  5042.6 2177.07  5063.5 2189.81  5077.8 2191.00
  5120.6 2201.04  5163.4 2206.77  5227.0 2213.53  5305.0 2216.49  5319.2 2218.21
  5382.9 2221.26  5425.7 2225.96  5432.3 2224.87  5440.0 2226.48  5449.9 2225.66
#Mann=3,-1,0
  4255.3     0.1       0  4988.6    0.05       0  5011.1     0.1       0
Bank Sta=4988.6,5011.1
Exp/Cntr=0.3,0.1

Type RM Length L Ch R = 1,23920,542,542,542
BEGIN DESCRIPTION:
Stream0095 42.0
END DESCRIPTION:
XS GIS Cut Line= 3
      1779025.01     13910775.00      1779425.00     13910825.00
      1779825.00     13910975.00
#Sta/Elev= 30
  4596.9 2186.64  4727.9 2179.85  4758.1 2179.50  4795.9 2176.87  4828.7 2175.89
  4869.0 2171.09  4889.1 2166.31  4899.2 2164.91  4919.4 2164.53  4939.5 2162.12
  4969.8 2161.35  4978.7 2160.11  4979.2 2159.61  5001.2 2160.11  5032.0 2161.09
  5045.4 2163.04  5064.1 2170.30  5070.3 2173.69  5085.4 2177.30  5125.5 2189.14
  5210.9 2206.15  5216.3 2206.15  5241.2 2211.36  5271.5 2214.01  5296.4 2219.00
  5301.7 2218.70  5320.4 2221.94  5326.6 2224.27  5373.8 2228.80  5427.2 2231.09
#Mann=3,-1,0
  4596.9     0.1       0  4978.7    0.05       0  5001.2     0.1       0
Bank Sta=4978.7,5001.2
Exp/Cntr=0.3,0.1

Type RM Length L Ch R = 1,23378,570,570,570
BEGIN DESCRIPTION:
Stream0095 41.0
END DESCRIPTION:
XS GIS Cut Line= 3
      1778774.97     13911275.00      1779175.00     13911275.00
      1779874.98     13911125.00
#Sta/Elev= 30
  4600.3 2190.97  4650.3 2189.26  4710.3 2185.24  4830.3 2182.43  4870.3 2180.02
  4940.3 2170.01  4970.3 2161.39  4979.0 2157.55  4979.5 2157.05  5001.6 2157.55
  5041.2 2161.26  5112.8 2163.94  5118.8 2165.44  5133.3 2165.85  5163.1 2169.14
  5168.2 2168.52  5204.9 2171.52  5212.5 2173.12  5245.8 2175.50  5306.3 2182.92
  5360.8 2187.66  5399.2 2192.71  5405.1 2194.60  5504.0 2207.32  5548.3 2214.65
  5583.3 2217.85  5603.7 2221.43  5634.4 2224.52  5685.5 2232.93  5716.2 2235.47
#Mann=3,-1,0
  4600.3     0.1       0  4979.0    0.05       0  5001.6     0.1       0
Bank Sta=4979,5001.6
Exp/Cntr=0.3,0.1

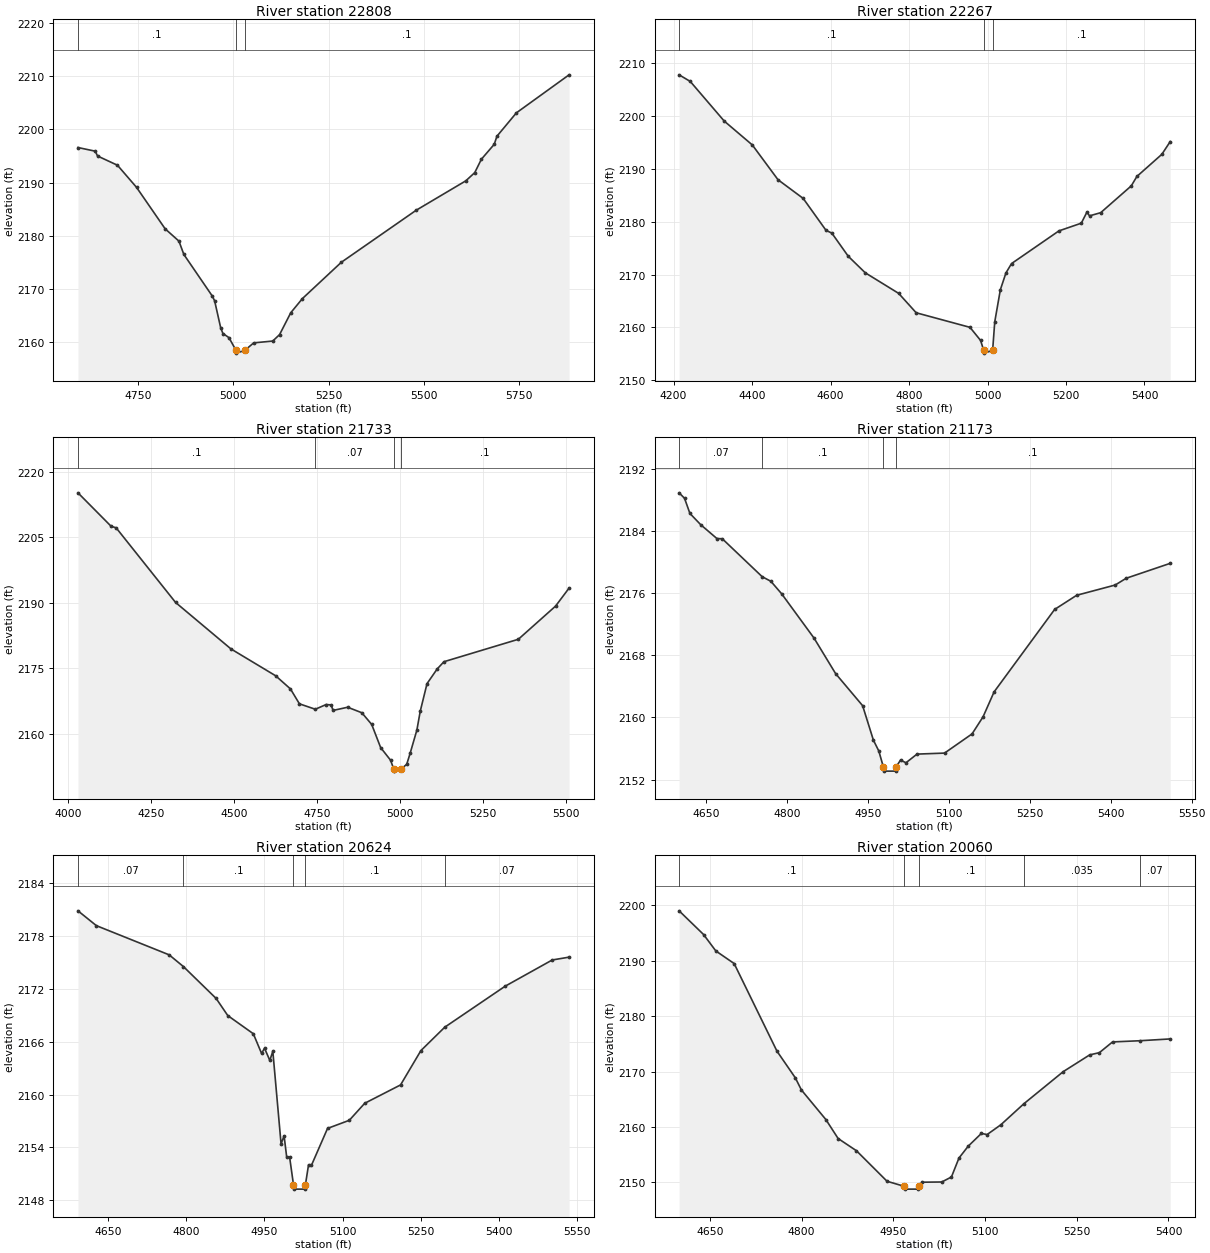
Type RM Length L Ch R = 1,22808,541,541,541
BEGIN DESCRIPTION:
Stream0095 40.0
END DESCRIPTION:
XS GIS Cut Line= 3
      1778625.00     13911575.00      1779068.69     13911827.21
      1779830.43     13911978.59
#Sta/Elev= 30
  4593.1 2196.60  4638.5 2195.91  4644.3 2195.01  4696.6 2193.27  4746.6 2189.11
  4821.6 2181.31  4857.7 2179.00  4870.6 2176.49  4945.6 2168.62  4951.3 2167.75
  4967.2 2162.67  4973.0 2161.63  4988.8 2160.85  5007.4 2158.44  5007.9 2157.94
  5030.0 2158.44  5053.7 2159.87  5103.5 2160.21  5121.5 2161.43  5150.7 2165.53
  5181.3 2168.20  5283.2 2175.02  5479.5 2184.81  5609.5 2190.34  5632.9 2191.88
  5650.3 2194.40  5684.0 2197.21  5691.0 2198.72  5742.0 2203.12  5880.1 2210.27
#Mann=3,-1,0
  4593.1     0.1       0  5007.4    0.05       0  5030.0     0.1       0
Bank Sta=5007.4,5030
Exp/Cntr=0.3,0.1

Type RM Length L Ch R = 1,22267,534,534,534
BEGIN DESCRIPTION:
Stream0095 39.0
END DESCRIPTION:
XS GIS Cut Line= 3
      1778275.00     13911825.00      1778925.00     13912275.00
      1779224.97     13912624.96
#Sta/Elev= 30
  4214.1 2207.71  4242.5 2206.46  4329.0 2198.98  4400.6 2194.47  4466.1 2187.90
  4530.3 2184.37  4588.4 2178.35  4603.3 2177.82  4645.2 2173.44  4688.4 2170.33
  4773.6 2166.44  4818.2 2162.78  4955.3 2160.03  4982.4 2157.55  4990.3 2155.66
  4990.8 2155.16  5013.0 2155.66  5018.4 2161.07  5032.7 2167.13  5046.9 2170.30
  5061.2 2172.07  5181.9 2178.24  5239.0 2179.70  5253.3 2181.79  5259.9 2181.08
  5288.4 2181.68  5366.3 2186.74  5380.6 2188.52  5444.2 2192.70  5465.6 2195.11
#Mann=3,-1,0
  4214.1     0.1       0  4990.3    0.05       0  5013.0     0.1       0
Bank Sta=4990.3,5013
Exp/Cntr=0.3,0.1

Type RM Length L Ch R = 1,21733,560,560,560
BEGIN DESCRIPTION:
Stream0095 38.0
END DESCRIPTION:
XS GIS Cut Line= 3
      1778075.01     13911875.01      1778625.00     13912675.00
      1779124.98     13912775.00
#Sta/Elev= 30
  4029.2 2215.16  4129.3 2207.48  4144.2 2207.15  4323.5 2190.04  4490.3 2179.40
  4625.2 2173.24  4669.9 2170.22  4696.9 2166.81  4744.8 2165.57  4777.4 2166.65
  4792.3 2166.56  4798.4 2165.30  4842.3 2166.03  4885.0 2164.77  4914.8 2162.09
  4941.8 2156.78  4971.6 2153.90  4981.2 2151.89  4981.7 2151.39  5003.9 2151.89
  5020.4 2152.96  5030.6 2155.45  5051.0 2160.80  5061.2 2165.13  5081.6 2171.44
  5112.2 2174.80  5132.6 2176.46  5356.9 2181.60  5469.1 2189.20  5509.9 2193.33
#Mann=4,-1,0
  4029.2     0.1       0  4744.8    0.07       0  4981.2    0.05       0
  5003.9     0.1       0
Bank Sta=4981.2,5003.9
Exp/Cntr=0.3,0.1

Type RM Length L Ch R = 1,21173,549,549,549
BEGIN DESCRIPTION:
Stream0095 37.0
END DESCRIPTION:
XS GIS Cut Line= 3
      1777924.95     13913125.00      1778325.00     13913125.00
      1778825.05     13913024.99
#Sta/Elev= 30
  4600.3 2188.90  4610.3 2188.20  4620.3 2186.25  4640.3 2184.80  4670.3 2183.02
  4680.3 2182.99  4754.2 2178.11  4770.3 2177.52  4790.3 2175.91  4850.3 2170.21
  4890.3 2165.64  4940.3 2161.52  4960.3 2157.08  4970.3 2155.69  4978.9 2153.60
  4979.4 2153.10  5001.3 2153.10  5001.8 2153.60  5010.5 2154.51  5020.7 2154.18
  5041.1 2155.29  5092.1 2155.42  5143.1 2157.89  5163.5 2160.09  5183.9 2163.29
  5296.1 2173.90  5336.9 2175.72  5408.3 2177.04  5428.7 2177.91  5510.3 2179.83
#Mann=4,-1,0
  4600.3    0.07       0  4754.2     0.1       0  4978.9    0.05       0
  5001.8     0.1       0
Bank Sta=4978.9,5001.8
Exp/Cntr=0.3,0.1

Type RM Length L Ch R = 1,20624,564,564,564
BEGIN DESCRIPTION:
Stream0095 36.0
END DESCRIPTION:
XS GIS Cut Line= 3
      1777925.01     13913425.01      1778275.00     13913625.00
      1778774.99     13913425.01
#Sta/Elev= 30
  4592.8 2180.82  4628.1 2179.14  4767.7 2175.83  4795.0 2174.50  4857.7 2170.89
  4880.0 2168.95  4929.0 2166.89  4944.8 2164.66  4950.5 2165.25  4960.6 2163.87
  4966.4 2164.90  4982.2 2154.40  4988.0 2155.32  4993.0 2152.90  4998.6 2152.90
  5006.0 2149.78  5006.5 2149.28  5028.4 2149.28  5028.9 2149.78  5034.9 2152.05
  5040.3 2151.96  5071.3 2156.16  5113.0 2157.08  5142.6 2159.01  5211.3 2161.09
  5250.3 2164.98  5296.0 2167.63  5411.9 2172.28  5502.1 2175.25  5534.4 2175.57
#Mann=5,-1,0
  4592.8    0.07       0  4795.0     0.1       0  5006.0    0.05       0
  5028.9     0.1       0  5296.0    0.07       0
Bank Sta=5006,5028.9
Exp/Cntr=0.3,0.1

Type RM Length L Ch R = 1,20060,501,501,501
BEGIN DESCRIPTION:
Stream0095 35.0
END DESCRIPTION:
XS GIS Cut Line= 3
      1778575.00     13914474.98      1778575.00     13914075.00
      1778925.00     13913875.00
#Sta/Elev= 30
  4599.8 2199.03  4639.8 2194.75  4659.8 2191.79  4689.8 2189.51  4759.8 2173.69
  4789.8 2168.88  4799.8 2166.68  4839.8 2161.34  4859.8 2157.92  4889.8 2155.71
  4939.8 2150.20  4968.2 2149.28  4968.7 2148.78  4990.8 2148.78  4991.3 2149.28
  4997.3 2150.03  5029.3 2150.07  5045.1 2150.97  5057.4 2154.39  5072.5 2156.53
  5094.1 2158.84  5103.4 2158.63  5125.8 2160.39  5163.6 2164.20  5228.0 2170.00
  5271.2 2173.02  5287.0 2173.42  5308.6 2175.36  5352.7 2175.57  5402.9 2175.90
#Mann=5,-1,0
  4599.8     0.1       0  4968.2    0.05       0  4991.3     0.1       0
  5163.6   0.035       0  5352.7    0.07       0
Bank Sta=4968.2,4991.3
Exp/Cntr=0.3,0.1

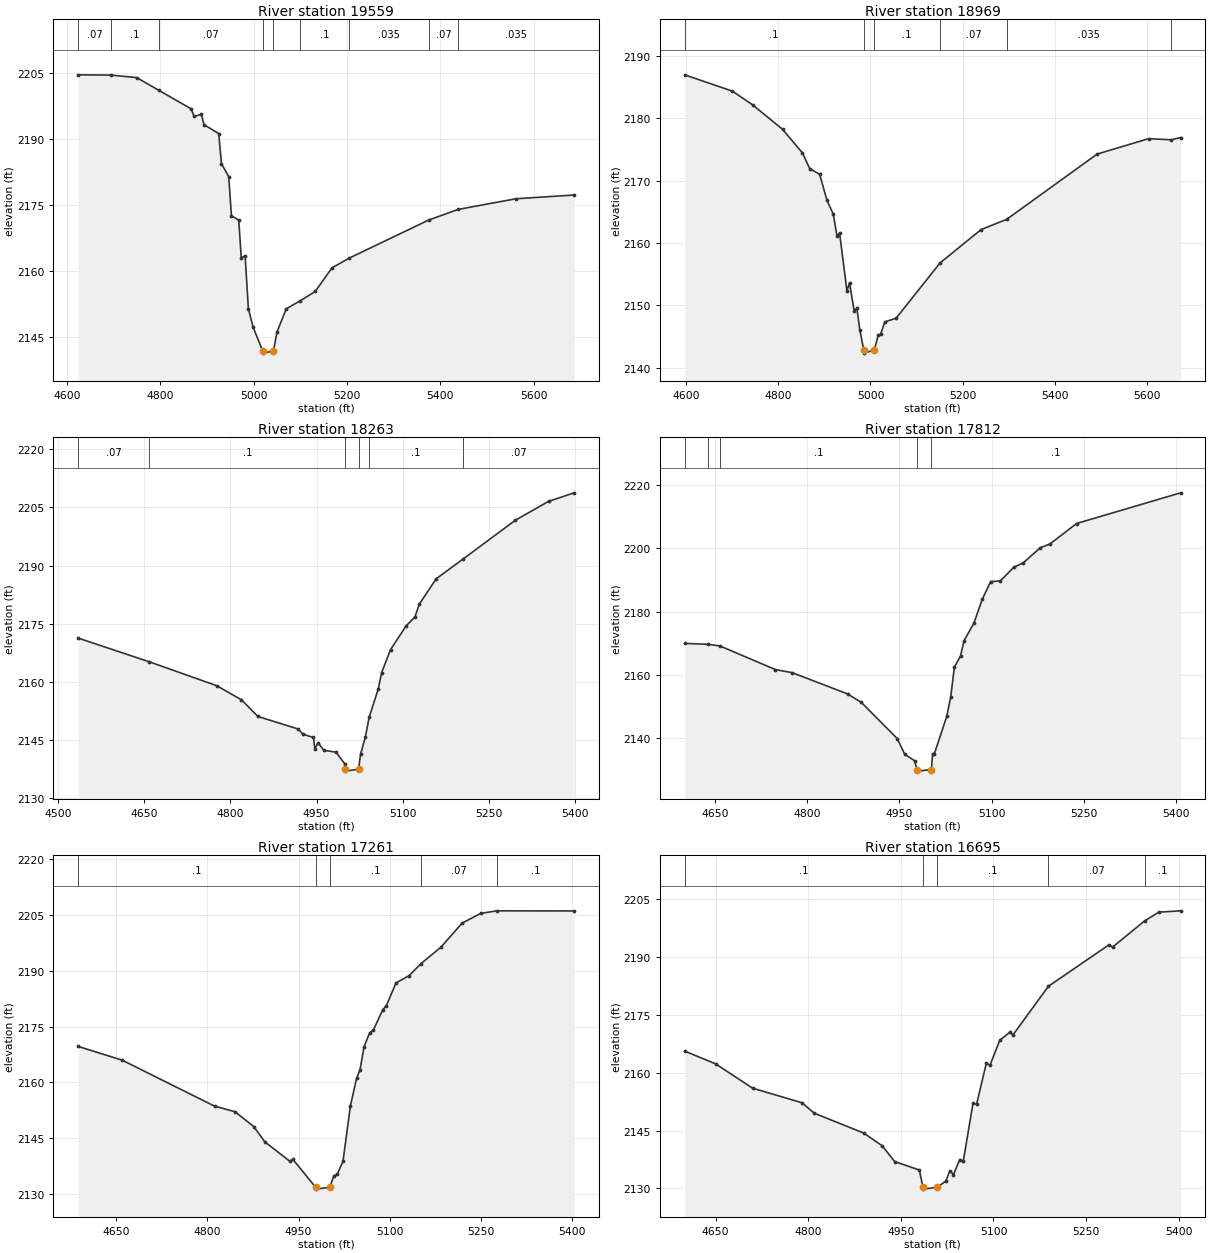
Type RM Length L Ch R = 1,19559,590,590,590
BEGIN DESCRIPTION:
Stream0095 34.0
END DESCRIPTION:
XS GIS Cut Line= 3
      1778624.98     13914575.01      1778929.27     13914396.86
      1779080.35     13913702.71
#Sta/Elev= 30
  4623.9 2204.69  4694.6 2204.63  4749.1 2204.06  4796.6 2201.17  4866.4 2196.92
  4872.2 2195.23  4887.9 2195.68  4893.7 2193.34  4925.1 2191.31  4930.9 2184.45
  4946.5 2181.54  4952.3 2172.64  4968.0 2171.60  4973.4 2163.07  4981.7 2163.48
  4988.6 2151.49  4998.9 2147.22  5019.3 2141.85  5019.8 2141.35  5042.4 2141.85
  5050.0 2146.15  5069.7 2151.43  5098.9 2153.21  5131.9 2155.38  5167.9 2160.76
  5204.7 2162.97  5375.1 2171.64  5438.4 2174.06  5561.8 2176.48  5686.9 2177.34
#Mann=9,-1,0
  4623.9    0.07       0  4694.6     0.1       0  4796.6    0.07       0
  5019.3    0.05       0  5042.4    0.07       0  5098.9     0.1       0
  5204.7   0.035       0  5375.1    0.07       0  5438.4   0.035       0
Bank Sta=5019.3,5042.4
Exp/Cntr=0.3,0.1

Type RM Length L Ch R = 1,18969,706,706,706
BEGIN DESCRIPTION:
Stream0095 33.0
END DESCRIPTION:
XS GIS Cut Line= 3
      1779275.02     13914674.97      1779475.00     13914325.00
      1779289.45     13913678.06
#Sta/Elev= 30
  4596.9 2186.97  4700.5 2184.35  4744.4 2182.15  4809.2 2178.24  4852.4 2174.45
  4868.2 2171.93  4889.8 2171.00  4905.7 2166.83  4919.4 2164.62  4927.3 2161.13
  4933.0 2161.59  4948.9 2152.33  4954.6 2153.60  4964.7 2149.08  4970.5 2149.57
  4976.9 2146.06  4985.5 2142.83  4986.0 2142.33  5008.6 2142.83  5016.8 2145.25
  5022.0 2145.35  5031.2 2147.34  5055.8 2147.94  5151.0 2156.80  5240.1 2162.15
  5295.6 2163.79  5491.9 2174.26  5603.5 2176.73  5652.6 2176.55  5673.0 2176.91
#Mann=6,-1,0
  4596.9     0.1       0  4985.5    0.05       0  5008.6     0.1       0
  5151.0    0.07       0  5295.6   0.035       0  5652.6    0.07       0
Bank Sta=4985.5,5008.6
Exp/Cntr=0.3,0.1

Type RM Length L Ch R = 1,18263,451,451,451
BEGIN DESCRIPTION:
Stream0095 32.0
END DESCRIPTION:
XS GIS Cut Line= 3
      1779825.02     13914574.98      1780087.31     13914264.33
      1780324.99     13913875.02
#Sta/Elev= 30
  4535.4 2171.29  4659.3 2165.16  4776.6 2158.99  4819.4 2155.36  4848.0 2151.07
  4918.3 2147.81  4926.1 2146.49  4944.5 2145.64  4947.1 2142.78  4952.9 2144.29
  4962.5 2142.35  4983.9 2141.85  4999.3 2138.79  4999.8 2137.46  5000.3 2136.96
  5023.1 2137.46  5026.5 2141.28  5034.9 2145.78  5041.6 2150.90  5057.4 2158.20
  5063.2 2162.39  5078.7 2168.32  5105.9 2174.45  5121.3 2176.78  5128.6 2180.01
  5158.1 2186.60  5204.2 2191.62  5295.6 2201.68  5353.6 2206.58  5398.1 2208.78
#Mann=6,-1,0
  4535.4    0.07       0  4659.3     0.1       0  4999.8    0.05       0
  5023.1     0.1       0  5041.6     0.1       0  5204.2    0.07       0
Bank Sta=4999.8,5023.1
Exp/Cntr=0.3,0.1

Type RM Length L Ch R = 1,17812,551,551,551
BEGIN DESCRIPTION:
Stream0095 31.0
END DESCRIPTION:
XS GIS Cut Line= 3
      1780075.03     13914724.98      1780425.00     13914525.00
      1780625.00     13914174.99
#Sta/Elev= 30
  4600.9 2169.93  4638.8 2169.64  4658.3 2169.11  4748.4 2161.65  4775.8 2160.67
  4865.8 2153.95  4888.1 2151.27  4946.4 2139.86  4958.6 2134.89  4974.5 2132.87
  4978.7 2130.06  4979.2 2129.56  5002.0 2130.06  5004.0 2135.10  5006.9 2135.10
  5027.0 2146.90  5033.5 2153.14  5039.3 2162.42  5049.3 2165.96  5055.1 2170.80
  5070.9 2176.24  5084.6 2183.84  5098.3 2189.46  5114.1 2189.67  5135.7 2193.95
  5151.5 2195.42  5178.9 2200.15  5194.7 2201.34  5237.9 2207.81  5407.1 2217.51
#Mann=5,-1,0
  4600.9     0.1       0  4638.8    0.07       0  4658.3     0.1       0
  4978.7    0.05       0  5002.0     0.1       0
Bank Sta=4978.7,5002
Exp/Cntr=0.3,0.1

Type RM Length L Ch R = 1,17261,566,566,566
BEGIN DESCRIPTION:
Stream0095 30.0
END DESCRIPTION:
XS GIS Cut Line= 3
      1780174.95     13914924.99      1780575.00     13915025.00
      1780925.03     13914824.99
#Sta/Elev= 30
  4587.6 2169.68  4659.8 2166.00  4811.8 2153.65  4845.3 2152.15  4876.3 2148.16
  4894.3 2144.08  4935.5 2138.85  4940.7 2139.33  4978.0 2131.86  4978.5 2131.36
  5001.3 2131.86  5007.9 2134.89  5013.6 2135.38  5023.0 2138.86  5035.2 2153.74
  5045.3 2161.09  5051.1 2163.44  5057.5 2169.53  5066.9 2173.37  5072.7 2174.00
  5088.5 2179.58  5094.3 2180.61  5110.1 2186.73  5131.7 2188.70  5151.4 2191.94
  5184.2 2196.37  5218.8 2202.79  5249.7 2205.43  5276.6 2206.10  5403.1 2206.07
#Mann=5,-1,0
  4587.6     0.1       0  4978.0    0.05       0  5001.3     0.1       0
  5151.4    0.07       0  5276.6     0.1       0
Bank Sta=4978,5001.3
Exp/Cntr=0.3,0.1

Type RM Length L Ch R = 1,16695,546,546,546
BEGIN DESCRIPTION:
Stream0095 29.0
END DESCRIPTION:
XS GIS Cut Line= 3
      1780125.00     13915575.00      1780525.00     13915575.00
      1780874.99     13915375.01
#Sta/Elev= 30
  4600.0 2165.59  4650.0 2162.29  4710.0 2155.98  4790.0 2152.20  4810.0 2149.49
  4890.0 2144.34  4920.0 2141.04  4940.0 2136.97  4980.0 2134.77  4985.8 2130.32
  4986.3 2129.82  5009.3 2130.32  5023.0 2131.91  5029.5 2134.60  5035.3 2133.57
  5045.4 2137.48  5051.1 2137.02  5066.9 2152.06  5072.7 2151.81  5088.5 2162.46
  5094.3 2161.88  5110.1 2168.36  5126.0 2170.42  5131.7 2169.80  5189.0 2182.39
  5287.2 2193.15  5293.0 2192.55  5345.0 2199.35  5367.8 2201.60  5403.1 2201.94
#Mann=5,-1,0
  4600.0     0.1       0  4985.8    0.05       0  5009.3     0.1       0
  5189.0    0.07       0  5345.0     0.1       0
Bank Sta=4985.8,5009.3
Exp/Cntr=0.3,0.1

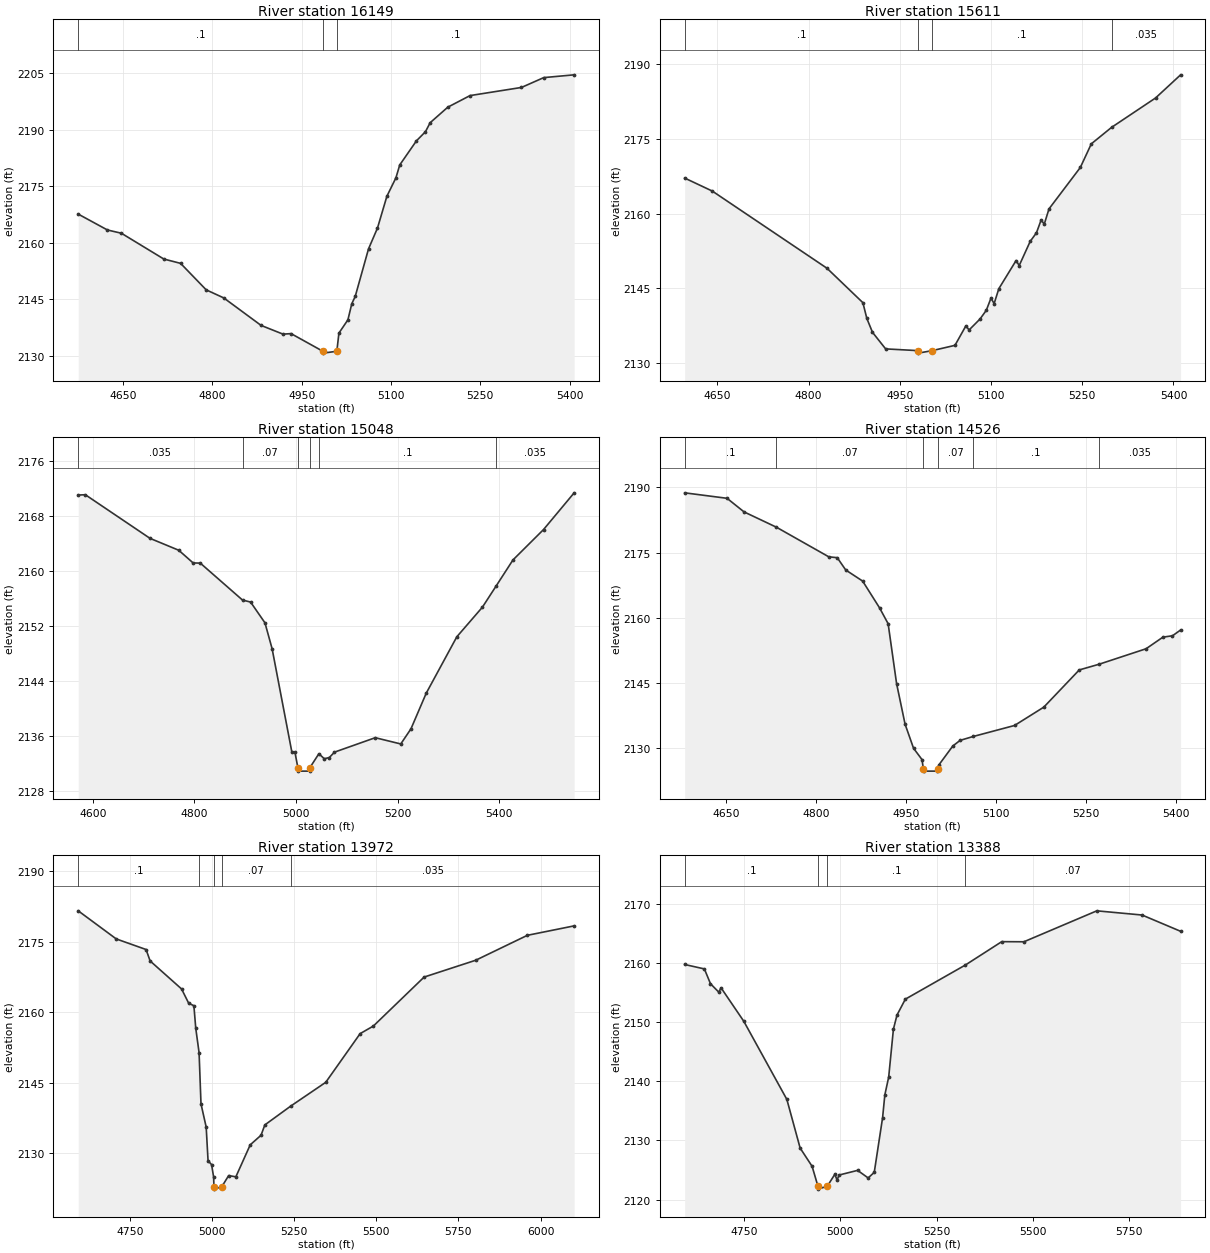
Type RM Length L Ch R = 1,16149,538,538,538
BEGIN DESCRIPTION:
Stream0095 28.0
END DESCRIPTION:
XS GIS Cut Line= 3
      1780025.02     13915825.01      1780375.00     13916075.00
      1780724.99     13916275.00
#Sta/Elev= 30
  4574.6 2167.66  4623.7 2163.44  4647.1 2162.58  4718.4 2155.73  4746.6 2154.58
  4789.6 2147.55  4819.1 2145.41  4881.8 2138.11  4918.7 2135.79  4932.2 2135.93
  4985.6 2131.25  4986.1 2130.75  5009.1 2131.25  5012.6 2136.07  5027.7 2139.59
  5034.2 2143.85  5040.0 2145.81  5062.3 2158.41  5077.4 2163.96  5093.2 2172.40
  5108.4 2177.30  5114.8 2180.71  5142.9 2187.12  5158.0 2189.53  5165.9 2191.92
  5195.5 2196.04  5232.9 2199.12  5319.3 2201.28  5356.7 2203.89  5407.8 2204.63
#Mann=3,-1,0
  4574.6     0.1       0  4985.6    0.05       0  5009.1     0.1       0
Bank Sta=4985.6,5009.1
Exp/Cntr=0.3,0.1

Type RM Length L Ch R = 1,15611,563,563,563
BEGIN DESCRIPTION:
Stream0095 27.0
END DESCRIPTION:
XS GIS Cut Line= 3
      1779774.98     13916324.99      1780125.00     13916525.00
      1780524.96     13916425.01
#Sta/Elev= 30
  4596.4 2167.11  4641.8 2164.50  4830.4 2149.03  4889.4 2142.13  4895.9 2138.97
  4905.2 2136.19  4926.8 2132.87  4979.9 2132.52  4980.4 2132.02  5003.4 2132.52
  5040.8 2133.58  5058.8 2137.50  5064.0 2136.66  5082.0 2138.86  5092.3 2140.60
  5100.0 2143.04  5105.2 2141.95  5112.9 2144.93  5141.3 2150.58  5146.4 2149.57
  5164.5 2154.42  5174.8 2156.14  5182.5 2158.72  5187.6 2157.87  5195.4 2160.93
  5246.9 2169.23  5265.0 2173.97  5298.3 2177.27  5370.6 2183.16  5411.8 2187.80
#Mann=4,-1,0
  4596.4     0.1       0  4979.9    0.05       0  5003.4     0.1       0
  5298.3   0.035       0
Bank Sta=4979.9,5003.4
Exp/Cntr=0.3,0.1

Type RM Length L Ch R = 1,15048,522,522,522
BEGIN DESCRIPTION:
Stream0095 26.0
END DESCRIPTION:
XS GIS Cut Line= 3
      1779525.03     13916675.03      1779825.00     13916975.00
      1780375.01     13916925.00
#Sta/Elev= 30
  4571.2 2171.02  4585.3 2171.06  4712.6 2164.72  4769.2 2162.99  4797.4 2161.15
  4811.6 2161.12  4894.7 2155.75  4910.6 2155.46  4938.9 2152.44  4953.0 2148.67
  4991.9 2133.64  4997.9 2133.64  5003.7 2131.38  5004.2 2130.88  5026.8 2130.88
  5027.3 2131.38  5045.1 2133.41  5055.7 2132.68  5065.7 2132.86  5075.8 2133.64
  5156.1 2135.74  5206.3 2134.83  5226.4 2137.03  5256.5 2142.22  5316.7 2150.41
  5367.0 2154.71  5394.4 2157.83  5427.2 2161.58  5487.4 2166.00  5547.7 2171.34
#Mann=6,-1,0
  4571.2   0.035       0  4894.7    0.07       0  5003.7    0.05       0
  5027.3    0.07       0  5045.1     0.1       0  5394.4   0.035       0
Bank Sta=5003.7,5027.3
Exp/Cntr=0.3,0.1

Type RM Length L Ch R = 1,14526,554,554,554
BEGIN DESCRIPTION:
Stream0095 25.0
END DESCRIPTION:
XS GIS Cut Line= 3
      1779625.03     13917724.97      1779925.00     13917425.00
      1780274.97     13917225.02
#Sta/Elev= 30
  4580.6 2188.73  4651.3 2187.47  4679.6 2184.35  4733.6 2180.83  4821.0 2174.02
  4835.1 2173.82  4849.3 2170.99  4877.5 2168.44  4905.8 2162.26  4920.0 2158.64
  4934.1 2144.87  4948.3 2135.53  4962.4 2130.01  4976.5 2127.41  4978.8 2125.26
  4979.3 2124.76  5002.0 2124.76  5002.5 2125.26  5004.8 2126.22  5027.9 2130.54
  5040.1 2131.83  5061.8 2132.72  5130.8 2135.25  5179.7 2139.47  5238.8 2148.02
  5271.9 2149.33  5350.3 2152.89  5378.4 2155.56  5394.3 2155.87  5407.9 2157.20
#Mann=6,-1,0
  4580.6     0.1       0  4733.6    0.07       0  4978.8    0.05       0
  5002.5    0.07       0  5061.8     0.1       0  5271.9   0.035       0
Bank Sta=4978.8,5002.5
Exp/Cntr=0.3,0.1

Type RM Length L Ch R = 1,13972,584,584,584
BEGIN DESCRIPTION:
Stream0095 24.0
END DESCRIPTION:
XS GIS Cut Line= 4
      1779925.04     13918024.98      1780275.00     13917825.00
      1780475.00     13917375.00      1780656.90     13916788.99
#Sta/Elev= 30
  4593.1 2181.59  4708.9 2175.61  4799.6 2173.36  4811.9 2170.93  4907.6 2164.97
  4929.2 2161.94  4945.1 2161.40  4950.8 2156.59  4960.9 2151.41  4966.7 2140.53
  4982.5 2135.59  4988.2 2128.42  4998.9 2127.61  5005.1 2124.98  5006.2 2122.89
  5006.7 2122.39  5029.9 2122.89  5050.9 2125.27  5072.8 2125.01  5116.5 2131.81
  5149.4 2133.85  5161.0 2136.05  5239.9 2140.06  5346.3 2145.11  5451.0 2155.47
  5491.2 2157.08  5645.7 2167.50  5802.7 2171.08  5959.8 2176.38  6102.2 2178.39
#Mann=5,-1,0
  4593.1     0.1       0  4960.9    0.07       0  5006.2    0.05       0
  5029.9    0.07       0  5239.9   0.035       0
Bank Sta=5006.2,5029.9
Exp/Cntr=0.3,0.1

Type RM Length L Ch R = 1,13388,1146,1146,1146
BEGIN DESCRIPTION:
Stream0095 23.0
END DESCRIPTION:
XS GIS Cut Line= 4
      1780475.04     13918124.98      1780825.00     13917925.00
      1781175.00     13917725.00      1781631.90     13917578.48
#Sta/Elev= 30
  4596.9 2159.73  4648.0 2158.98  4663.8 2156.48  4685.4 2155.05  4691.2 2155.79
  4750.2 2150.13  4861.8 2136.93  4896.3 2128.70  4927.3 2125.62  4942.4 2122.26
  4942.9 2121.76  4966.8 2122.26  4986.3 2124.27  4992.1 2123.28  4997.1 2124.14
  5045.3 2124.93  5072.7 2123.65  5088.5 2124.60  5110.1 2133.83  5115.9 2137.68
  5125.9 2140.70  5138.2 2148.81  5147.5 2151.19  5169.1 2153.87  5324.8 2159.64
  5419.1 2163.59  5476.6 2163.57  5665.6 2168.80  5783.0 2168.09  5882.9 2165.34
#Mann=4,-1,0
  4596.9     0.1       0  4942.4    0.05       0  4966.8     0.1       0
  5324.8    0.07       0
Bank Sta=4942.4,4966.8
Exp/Cntr=0.3,0.1