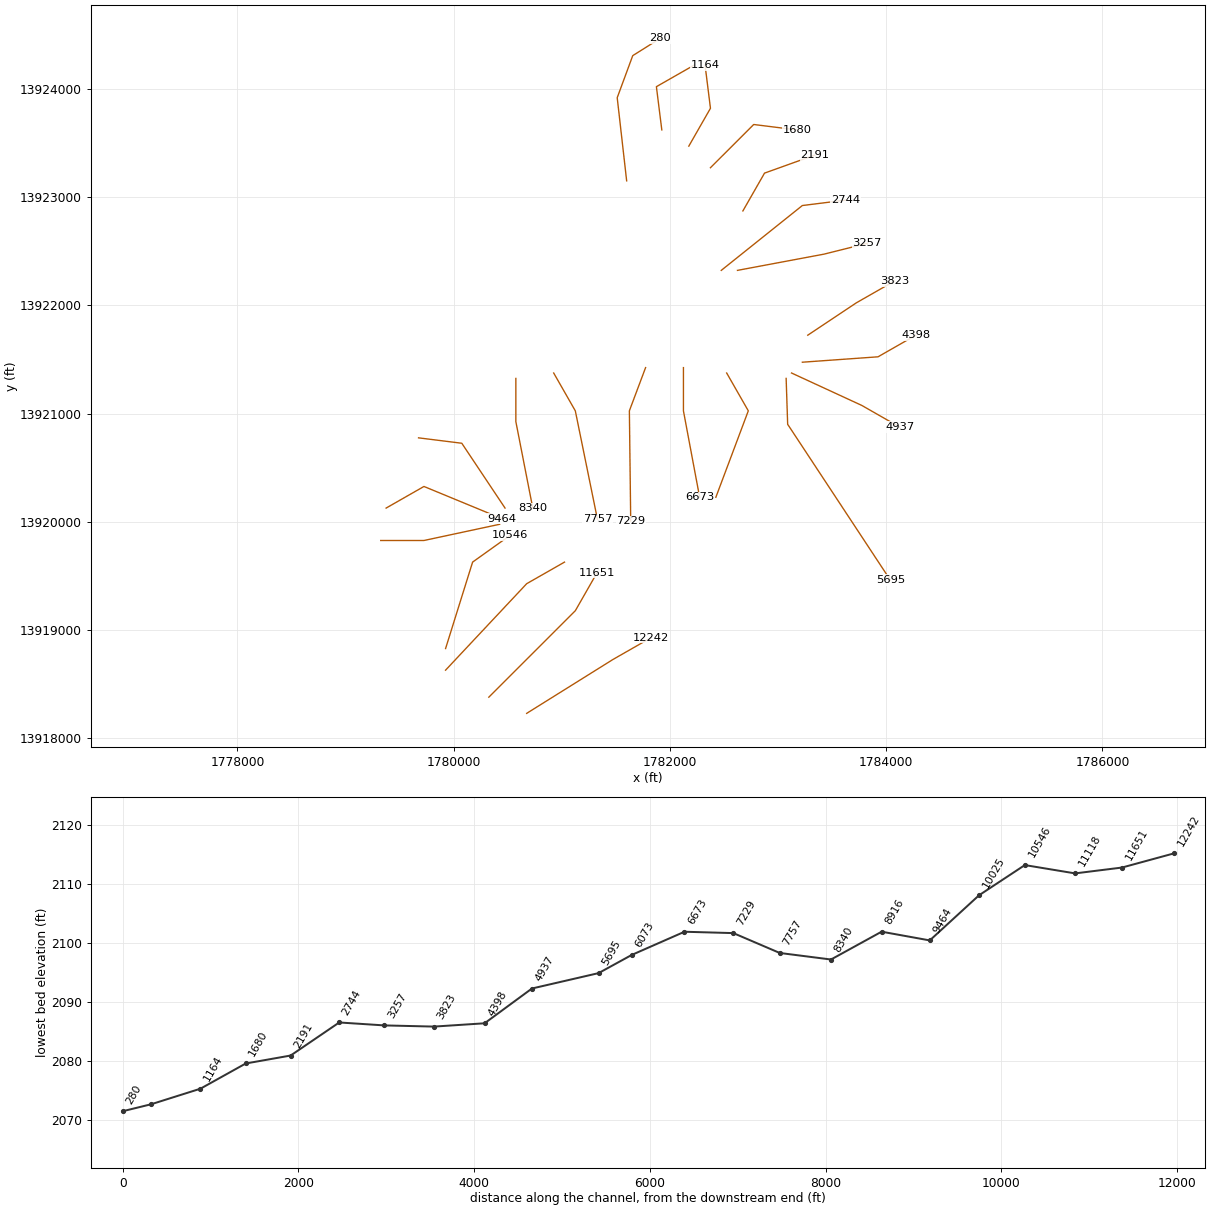
HEC-RAS study Stream0095.prj: Stream0095 Base Level Engineering

--- Stream0095.g01 (geometry) --- (continued)

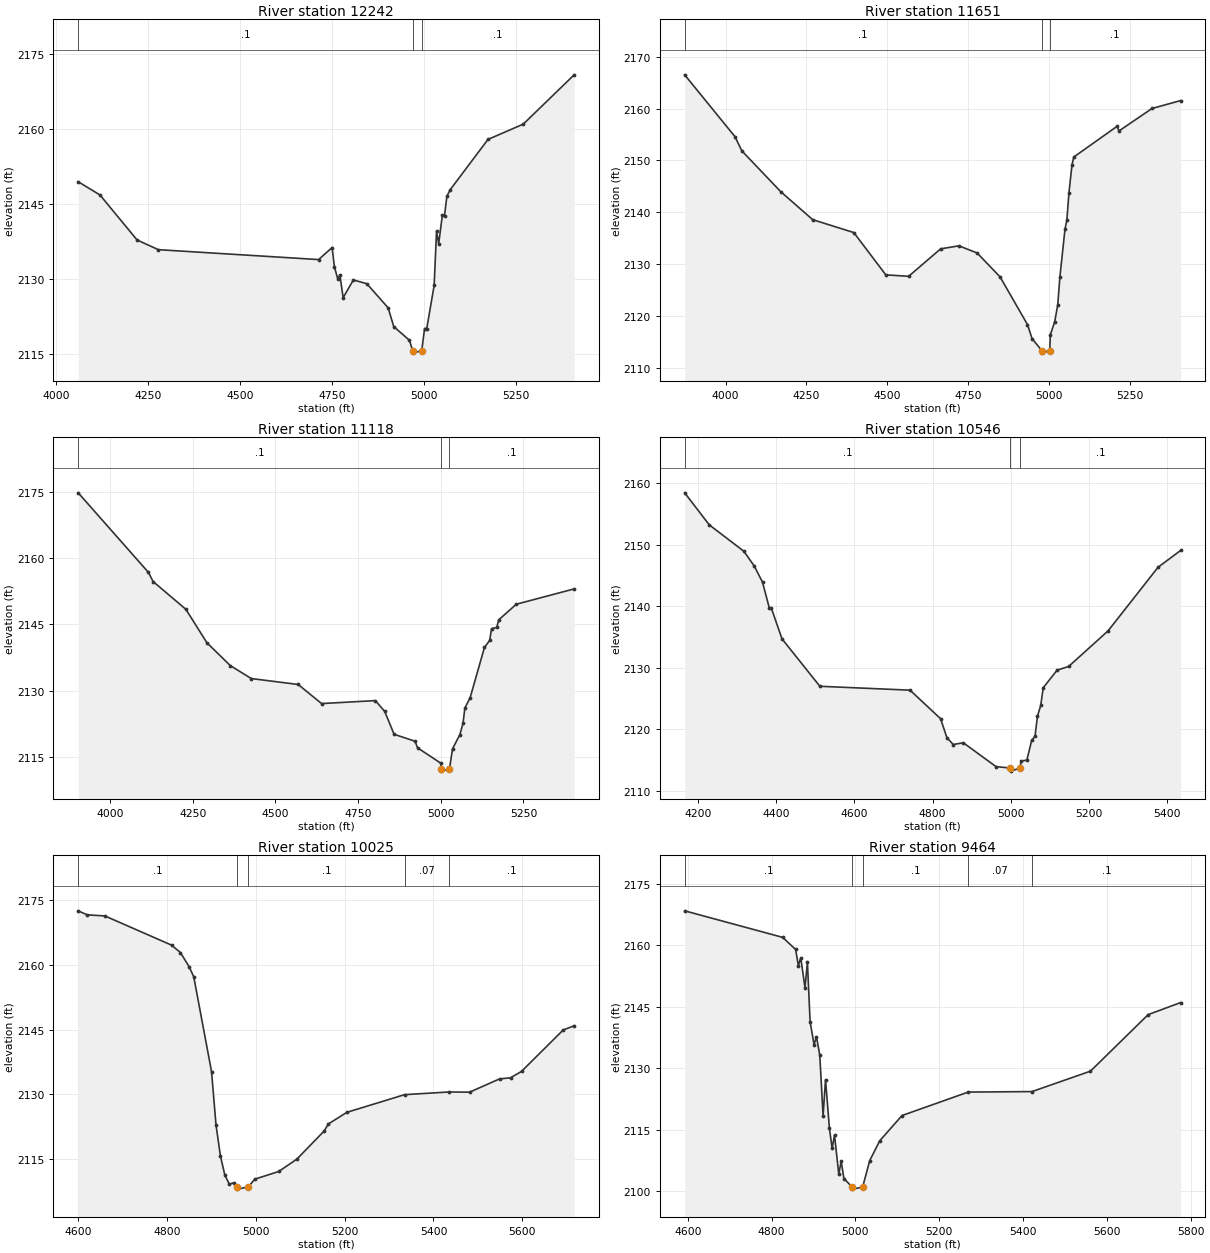
Type RM Length L Ch R = 1,12242,591,591,591
BEGIN DESCRIPTION:
Stream0095 22.0
END DESCRIPTION:
XS GIS Cut Line= 3
      1780675.01     13918225.01      1781475.00     13918725.00
      1781825.00     13918925.00
#Sta/Elev= 30
  4060.8 2149.47  4119.8 2146.83  4220.6 2137.83  4278.4 2135.89  4713.5 2133.91
  4750.1 2136.32  4756.5 2132.44  4765.4 2130.07  4771.3 2130.82  4780.1 2126.29
  4807.8 2129.83  4844.4 2129.09  4902.2 2124.27  4917.5 2120.52  4960.0 2117.78
  4968.9 2115.71  4969.4 2115.21  4993.5 2115.71  5001.2 2120.12  5007.1 2120.12
  5027.2 2128.75  5033.7 2139.60  5039.5 2137.09  5049.5 2142.79  5055.3 2142.72
  5061.8 2146.58  5071.1 2147.91  5173.4 2157.93  5269.1 2160.98  5407.3 2170.84
#Mann=3,-1,0
  4060.8     0.1       0  4968.9    0.05       0  4993.5     0.1       0
Bank Sta=4968.9,4993.5
Exp/Cntr=0.3,0.1

Type RM Length L Ch R = 1,11651,533,533,533
BEGIN DESCRIPTION:
Stream0095 21.0
END DESCRIPTION:
XS GIS Cut Line= 3
      1780324.97     13918374.97      1781125.00     13919175.00
      1781324.99     13919524.98
#Sta/Elev= 30
  3873.4 2166.50  4029.0 2154.57  4050.2 2151.84  4170.4 2143.97  4269.4 2138.56
  4396.7 2136.07  4495.7 2127.91  4566.4 2127.63  4665.4 2132.93  4722.0 2133.51
  4778.5 2132.12  4849.2 2127.52  4934.1 2118.32  4948.2 2115.61  4978.4 2113.31
  4978.9 2112.81  5003.0 2113.31  5004.8 2116.33  5018.5 2118.91  5027.8 2122.18
  5034.3 2127.48  5050.2 2136.76  5055.9 2138.44  5062.4 2143.76  5071.8 2149.14
  5077.5 2150.65  5211.4 2156.57  5217.2 2155.67  5319.4 2160.01  5407.9 2161.53
#Mann=3,-1,0
  3873.4     0.1       0  4978.4    0.05       0  5003.0     0.1       0
Bank Sta=4978.4,5003
Exp/Cntr=0.3,0.1

Type RM Length L Ch R = 1,11118,572,572,572
BEGIN DESCRIPTION:
Stream0095 20.0
END DESCRIPTION:
XS GIS Cut Line= 3
      1779924.97     13918624.97      1780675.00     13919425.00
      1781024.96     13919624.98
#Sta/Elev= 30
  3903.6 2174.77  4115.9 2156.78  4130.0 2154.71  4229.2 2148.42  4292.7 2140.86
  4363.5 2135.69  4427.0 2132.76  4568.7 2131.42  4639.5 2127.10  4802.2 2127.77
  4830.5 2125.32  4858.8 2120.15  4922.3 2118.58  4929.6 2117.10  5000.2 2113.61
  5001.6 2112.32  5002.1 2111.82  5026.3 2112.32  5035.5 2116.87  5057.8 2120.08
  5067.2 2122.63  5072.9 2126.11  5088.8 2128.43  5132.0 2139.79  5147.8 2141.39
  5153.6 2144.04  5169.4 2144.32  5175.2 2146.04  5228.4 2149.57  5403.3 2153.04
#Mann=3,-1,0
  3903.6     0.1       0  5001.6    0.05       0  5026.3     0.1       0
Bank Sta=5001.6,5026.3
Exp/Cntr=0.3,0.1

Type RM Length L Ch R = 1,10546,521,521,521
BEGIN DESCRIPTION:
Stream0095 19.0
END DESCRIPTION:
XS GIS Cut Line= 3
      1779925.01     13918825.03      1780175.00     13919625.00
      1780524.97     13919874.98
#Sta/Elev= 30
  4166.1 2158.43  4228.9 2153.23  4317.5 2148.94  4344.2 2146.52  4365.1 2143.92
  4382.4 2139.76  4387.7 2139.71  4414.9 2134.72  4511.8 2127.01  4742.3 2126.38
  4820.4 2121.75  4836.6 2118.68  4852.8 2117.55  4878.5 2117.84  4962.3 2113.96
  4999.2 2113.73  4999.7 2113.23  5023.9 2113.73  5026.3 2114.88  5041.1 2115.01
  5053.4 2118.21  5062.0 2118.91  5068.1 2122.11  5076.7 2123.93  5082.9 2126.77
  5118.5 2129.63  5148.0 2130.23  5248.8 2136.01  5376.6 2146.34  5434.3 2149.07
#Mann=3,-1,0
  4166.1     0.1       0  4999.2    0.05       0  5023.9     0.1       0
Bank Sta=4999.2,5023.9
Exp/Cntr=0.3,0.1

Type RM Length L Ch R = 1,10025,561,561,561
BEGIN DESCRIPTION:
Stream0095 18.0
END DESCRIPTION:
XS GIS Cut Line= 3
      1779324.96     13919825.00      1779725.00     13919825.00
      1780424.97     13919974.99
#Sta/Elev= 30
  4600.6 2172.45  4620.6 2171.52  4660.6 2171.27  4810.6 2164.52  4830.6 2162.81
  4850.6 2159.45  4860.6 2157.19  4900.6 2135.28  4910.6 2123.00  4920.6 2115.75
  4930.6 2111.33  4940.6 2109.25  4950.6 2109.59  4958.2 2108.61  4958.7 2108.11
  4983.0 2108.61  4998.1 2110.42  5051.8 2112.19  5092.7 2115.06  5154.0 2121.55
  5163.4 2123.18  5205.2 2125.87  5335.0 2129.95  5435.1 2130.57  5481.3 2130.53
  5548.6 2133.59  5573.4 2133.85  5598.1 2135.33  5691.8 2144.90  5716.5 2145.88
#Mann=5,-1,0
  4600.6     0.1       0  4958.2    0.05       0  4983.0     0.1       0
  5335.0    0.07       0  5435.1     0.1       0
Bank Sta=4958.2,4983
Exp/Cntr=0.3,0.1

Type RM Length L Ch R = 1,9464,548,548,548
BEGIN DESCRIPTION:
Stream0095 17.0
END DESCRIPTION:
XS GIS Cut Line= 3
      1779375.01     13920125.01      1779725.00     13920325.00
      1780446.67     13920026.94
#Sta/Elev= 30
  4592.4 2168.41  4826.3 2161.93  4857.3 2158.97  4863.8 2155.01  4869.5 2156.95
  4879.6 2149.62  4885.4 2155.85  4891.8 2141.36  4901.2 2135.74  4907.0 2137.66
  4914.9 2133.17  4922.8 2118.33  4928.6 2127.19  4937.9 2115.32  4944.4 2110.40
  4950.1 2113.66  4960.2 2104.13  4966.0 2107.27  4972.5 2103.04  4992.4 2100.95
  4992.9 2100.45  5017.2 2100.95  5034.1 2107.41  5058.0 2112.25  5111.2 2118.42
  5269.3 2124.15  5421.5 2124.27  5561.1 2129.26  5698.8 2143.06  5776.3 2146.01
#Mann=5,-1,0
  4592.4     0.1       0  4992.4    0.05       0  5017.2     0.1       0
  5269.3    0.07       0  5421.5     0.1       0
Bank Sta=4992.4,5017.2
Exp/Cntr=0.3,0.1

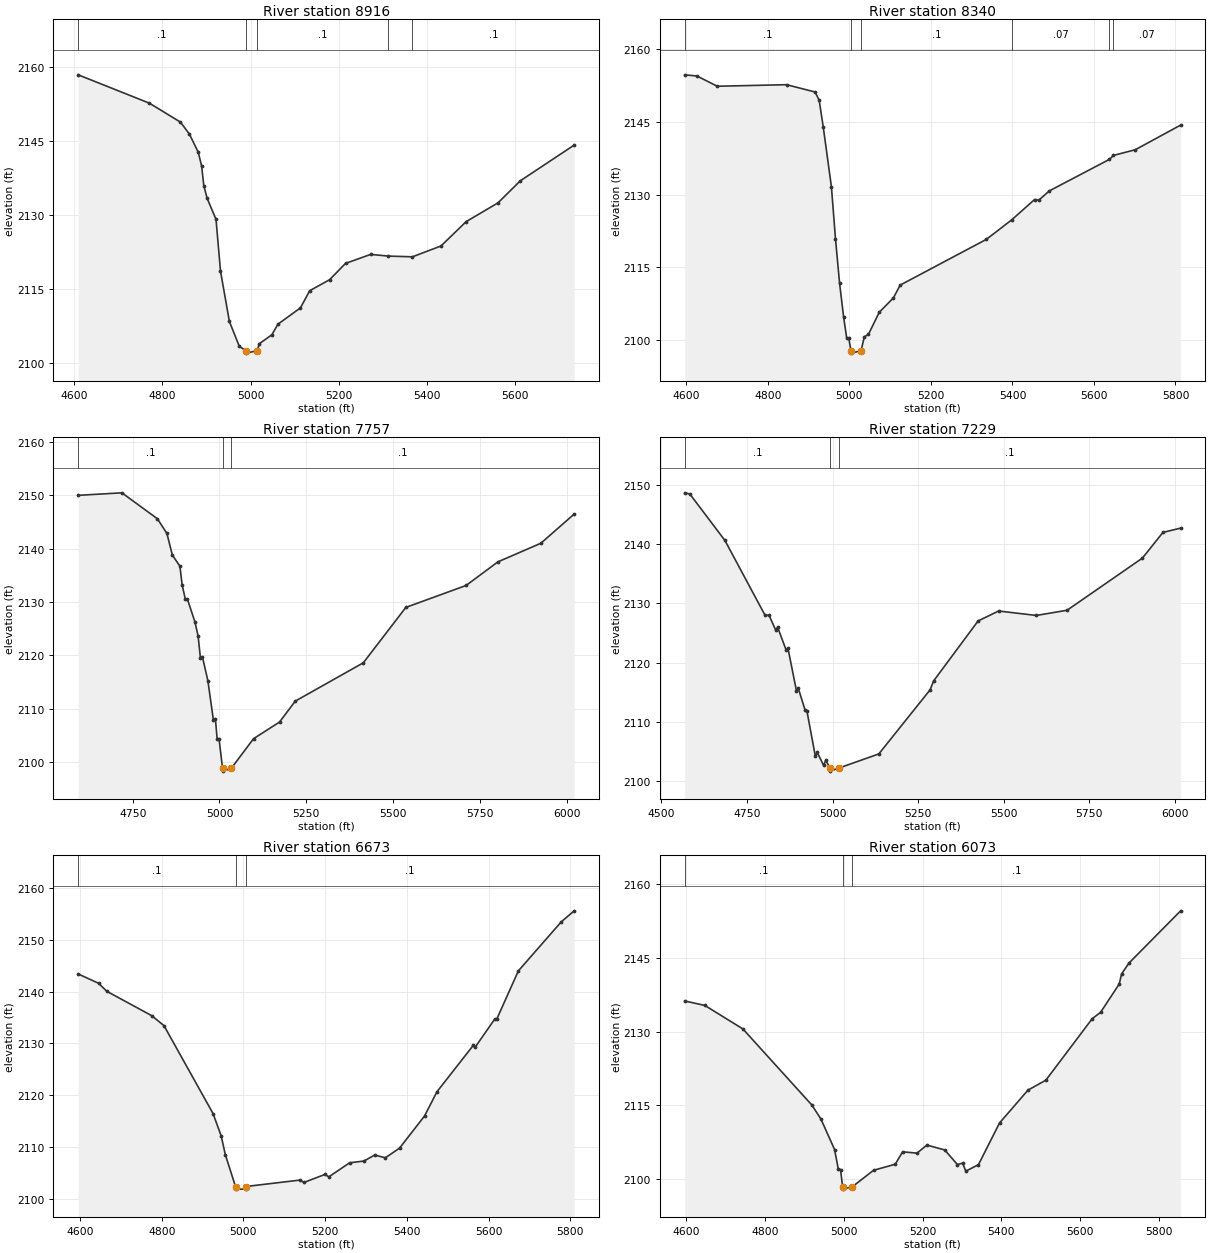
Type RM Length L Ch R = 1,8916,576,576,576
BEGIN DESCRIPTION:
Stream0095 16.0
END DESCRIPTION:
XS GIS Cut Line= 3
      1779674.99     13920775.00      1780075.00     13920725.00
      1780474.98     13920125.03
#Sta/Elev= 30
  4609.0 2158.48  4770.3 2152.72  4840.8 2148.87  4861.0 2146.44  4881.1 2142.75
  4888.7 2139.98  4893.7 2135.97  4901.3 2133.37  4921.4 2129.11  4931.5 2118.62
  4951.7 2108.36  4974.3 2103.28  4989.6 2102.43  4990.1 2101.93  5014.4 2102.43
  5019.6 2103.84  5048.2 2105.68  5061.7 2107.81  5112.8 2111.13  5133.8 2114.62
  5178.9 2116.85  5214.9 2120.16  5272.0 2121.99  5312.0 2121.65  5366.6 2121.50
  5431.3 2123.70  5488.4 2128.65  5560.5 2132.46  5611.5 2136.97  5733.2 2144.20
#Mann=5,-1,0
  4609.0     0.1       0  4989.6    0.05       0  5014.4     0.1       0
  5312.0    0.07       0  5366.6     0.1       0
Bank Sta=4989.6,5014.4
Exp/Cntr=0.3,0.1

Type RM Length L Ch R = 1,8340,583,583,583
BEGIN DESCRIPTION:
Stream0095 15.0
END DESCRIPTION:
XS GIS Cut Line= 3
      1780575.00     13921324.96      1780575.00     13920925.00
      1780731.74     13920123.34
#Sta/Elev= 30
  4595.8 2154.75  4625.8 2154.51  4675.8 2152.39  4845.8 2152.71  4915.8 2151.20
  4925.8 2149.49  4935.8 2143.95  4955.8 2131.62  4965.8 2120.86  4975.8 2111.71
  4985.8 2104.65  4993.3 2100.36  4998.3 2100.36  5003.7 2097.71  5004.2 2097.21
  5028.6 2097.71  5036.5 2100.57  5046.7 2101.09  5073.1 2105.65  5107.8 2108.62
  5124.6 2111.28  5335.8 2120.72  5398.1 2124.76  5454.3 2128.97  5464.5 2128.82
  5490.4 2130.75  5637.9 2137.27  5647.9 2138.09  5701.6 2139.27  5812.6 2144.36
#Mann=6,-1,0
  4595.8     0.1       0  5003.7    0.05       0  5028.6     0.1       0
  5398.1    0.07       0  5637.9     0.1       0  5647.9    0.07       0
Bank Sta=5003.7,5028.6
Exp/Cntr=0.3,0.1

Type RM Length L Ch R = 1,7757,528,528,528
BEGIN DESCRIPTION:
Stream0095 14.0
END DESCRIPTION:
XS GIS Cut Line= 3
      1780924.99     13921375.01      1781125.00     13921025.00
      1781329.97     13920019.82
#Sta/Elev= 30
  4592.9 2149.99  4718.9 2150.46  4821.1 2145.60  4848.5 2142.85  4864.3 2138.77
  4885.9 2136.73  4892.4 2133.20  4901.7 2130.49  4907.5 2130.54  4929.1 2126.30
  4938.4 2123.62  4944.9 2119.59  4950.7 2119.75  4966.5 2115.27  4982.4 2107.90
  4988.1 2108.15  4993.2 2104.40  4998.6 2104.40  5008.8 2098.82  5009.3 2098.32
  5033.7 2098.82  5098.1 2104.40  5172.9 2107.51  5218.4 2111.44  5414.5 2118.62
  5536.9 2128.99  5710.4 2133.10  5802.3 2137.53  5925.9 2141.01  6021.9 2146.48
#Mann=3,-1,0
  4592.9     0.1       0  5008.8    0.05       0  5033.7     0.1       0
Bank Sta=5008.8,5033.7
Exp/Cntr=0.3,0.1

Type RM Length L Ch R = 1,7229,556,556,556
BEGIN DESCRIPTION:
Stream0095 13.0
END DESCRIPTION:
XS GIS Cut Line= 3
      1781775.00     13921425.00      1781625.00     13921025.00
      1781637.45     13920003.38
#Sta/Elev= 30
  4568.0 2148.60  4583.1 2148.40  4685.5 2140.58  4803.0 2127.94  4814.5 2127.96
  4834.1 2125.44  4839.5 2125.96  4864.4 2122.10  4869.7 2122.42  4894.6 2115.21
  4900.0 2115.64  4919.6 2112.01  4924.9 2111.90  4949.8 2104.18  4955.2 2104.86
  4973.8 2102.66  4980.1 2103.52  4992.8 2102.19  4993.3 2101.69  5017.7 2102.19
  5135.2 2104.59  5285.2 2115.41  5295.2 2116.89  5425.2 2127.00  5485.2 2128.68
  5595.2 2127.93  5685.3 2128.81  5905.3 2137.60  5965.3 2141.93  6016.9 2142.65
#Mann=3,-1,0
  4568.0     0.1       0  4992.8    0.05       0  5017.7     0.1       0
Bank Sta=4992.8,5017.7
Exp/Cntr=0.3,0.1

Type RM Length L Ch R = 1,6673,600,600,600
BEGIN DESCRIPTION:
Stream0095 12.0
END DESCRIPTION:
XS GIS Cut Line= 3
      1782125.00     13921424.98      1782125.00     13921025.00
      1782275.00     13920225.02
#Sta/Elev= 30
  4595.6 2143.39  4645.6 2141.59  4665.6 2140.05  4775.6 2135.35  4805.6 2133.42
  4925.6 2116.49  4945.6 2112.17  4955.6 2108.58  4980.6 2102.42  4981.1 2101.92
  5005.1 2101.92  5005.6 2102.42  5138.0 2103.66  5148.2 2103.21  5199.1 2104.74
  5209.2 2104.30  5260.1 2107.00  5294.9 2107.33  5321.2 2108.49  5347.4 2107.96
  5382.2 2109.83  5443.2 2116.01  5473.8 2120.70  5562.8 2129.65  5567.9 2129.35
  5615.4 2134.73  5620.4 2134.75  5673.0 2143.99  5778.1 2153.45  5809.5 2155.56
#Mann=3,-1,0
  4595.6     0.1       0  4980.6    0.05       0  5005.6     0.1       0
Bank Sta=4980.6,5005.6
Exp/Cntr=0.3,0.1

Type RM Length L Ch R = 1,6073,378,378,378
BEGIN DESCRIPTION:
Stream0095 11.0
END DESCRIPTION:
XS GIS Cut Line= 3
      1782525.00     13921375.00      1782725.00     13921025.00
      1782425.00     13920225.01
#Sta/Elev= 30
  4596.9 2136.26  4648.0 2135.35  4744.5 2130.57  4919.4 2115.09  4942.4 2112.24
  4977.0 2106.04  4986.3 2102.12  4992.1 2101.97  4997.3 2098.49  4997.8 2097.99
  5022.3 2098.49  5075.7 2101.82  5130.8 2103.05  5149.5 2105.58  5186.0 2105.31
  5210.9 2106.94  5256.3 2105.96  5288.4 2102.99  5301.7 2103.27  5309.7 2101.65
  5341.8 2102.96  5395.2 2111.44  5467.3 2118.12  5512.7 2120.15  5630.1 2132.64
  5651.5 2133.95  5698.7 2139.70  5704.9 2141.79  5723.6 2143.98  5854.4 2154.59
#Mann=3,-1,0
  4596.9     0.1       0  4997.3    0.05       0  5022.3     0.1       0
Bank Sta=4997.3,5022.3
Exp/Cntr=0.3,0.1

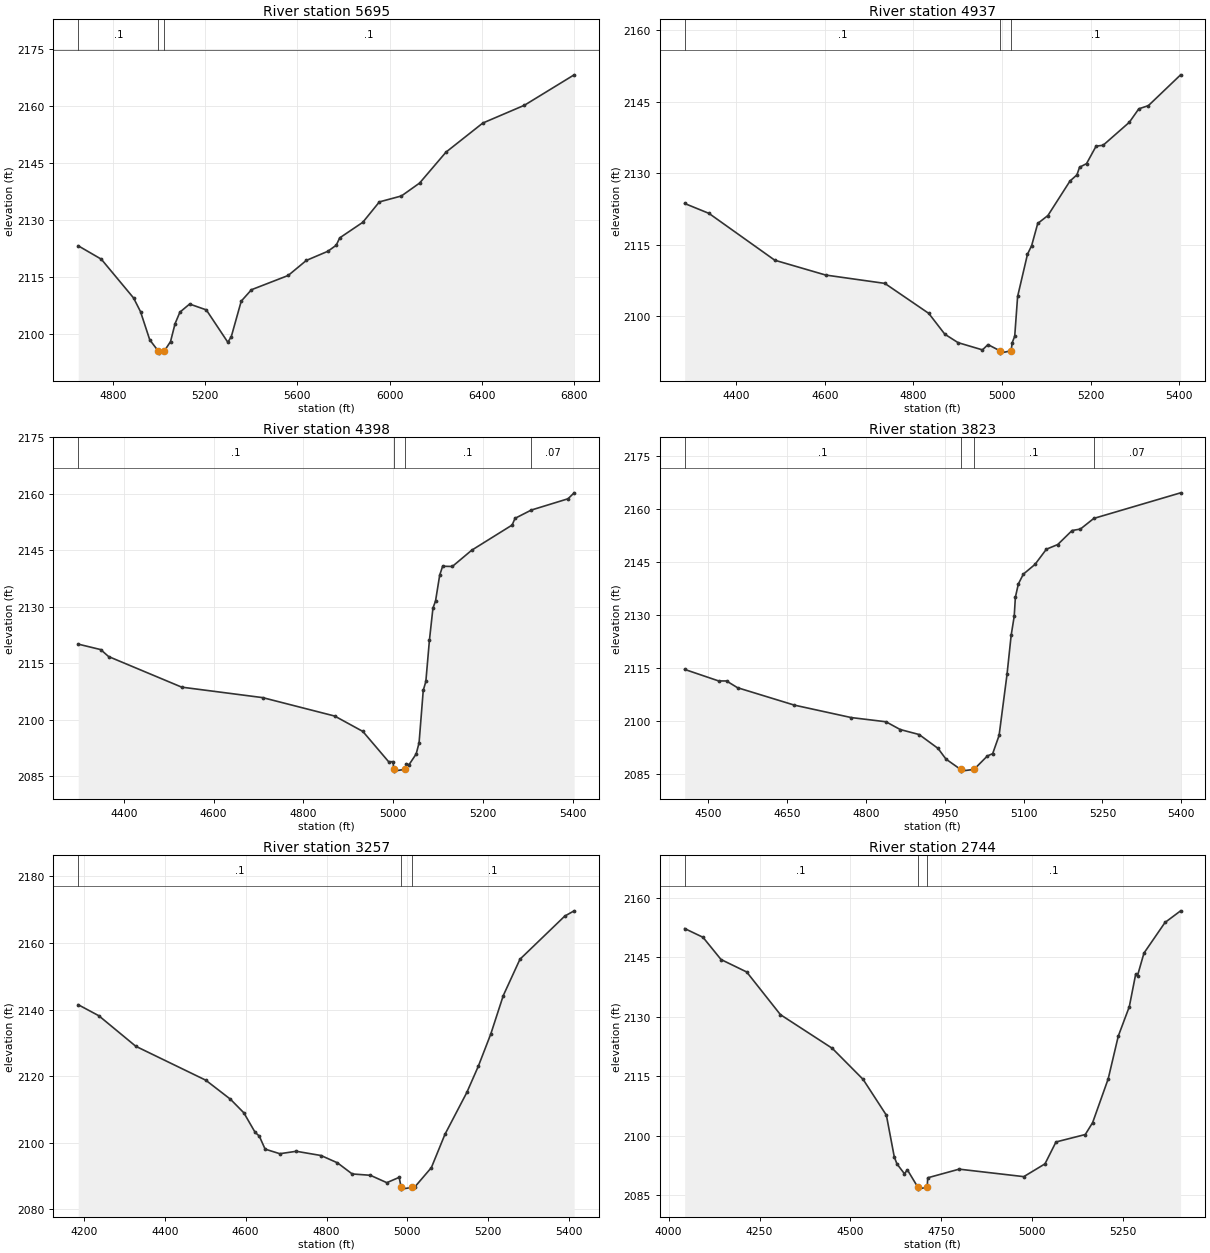
Type RM Length L Ch R = 1,5695,758,758,758
BEGIN DESCRIPTION:
Stream0095 10.0
END DESCRIPTION:
XS GIS Cut Line= 3
      1783075.00     13921324.98      1783089.11     13920900.54
      1784038.13     13919459.78
#Sta/Elev= 30
  4649.8 2123.15  4749.8 2119.63  4889.9 2109.41  4919.9 2105.81  4959.9 2098.40
  4997.5 2095.40  4998.0 2094.90  5022.5 2095.40  5050.0 2097.95  5069.7 2102.66
  5090.7 2105.69  5132.8 2107.82  5205.1 2106.28  5298.4 2097.76  5313.5 2099.26
  5356.5 2108.58  5400.9 2111.59  5560.1 2115.34  5638.8 2119.30  5732.1 2121.71
  5768.3 2123.30  5783.3 2125.23  5883.4 2129.33  5955.2 2134.70  6051.0 2136.27
  6129.7 2139.66  6244.1 2147.80  6403.7 2155.46  6584.4 2160.15  6799.7 2168.15
#Mann=3,-1,0
  4649.8     0.1       0  4997.5    0.05       0  5022.5     0.1       0
Bank Sta=4997.5,5022.5
Exp/Cntr=0.3,0.1

Type RM Length L Ch R = 1,4937,539,539,539
BEGIN DESCRIPTION:
Stream0095 9.0
END DESCRIPTION:
XS GIS Cut Line= 3
      1783124.96     13921375.02      1783775.00     13921075.00
      1784124.96     13920875.02
#Sta/Elev= 30
  4283.8 2123.68  4338.5 2121.61  4487.1 2111.78  4601.9 2108.67  4735.4 2106.92
  4834.5 2100.63  4870.8 2096.26  4900.6 2094.49  4955.7 2092.97  4968.1 2094.08
  4994.9 2092.79  4995.4 2092.29  5020.4 2092.79  5022.8 2094.48  5028.5 2095.85
  5035.0 2104.17  5057.3 2113.04  5066.7 2114.85  5080.4 2119.49  5103.4 2121.16
  5153.1 2128.38  5168.9 2129.69  5174.7 2131.28  5190.5 2132.04  5212.1 2135.71
  5227.9 2135.89  5287.0 2140.71  5308.5 2143.54  5330.1 2144.21  5402.8 2150.67
#Mann=3,-1,0
  4283.8     0.1       0  4994.9    0.05       0  5020.4     0.1       0
Bank Sta=4994.9,5020.4
Exp/Cntr=0.3,0.1

Type RM Length L Ch R = 1,4398,575,575,575
BEGIN DESCRIPTION:
Stream0095 8.0
END DESCRIPTION:
XS GIS Cut Line= 3
      1783225.01     13921475.00      1783925.00     13921525.00
      1784275.01     13921725.01
#Sta/Elev= 30
  4298.3 2120.10  4348.4 2118.65  4366.0 2116.80  4528.9 2108.68  4709.3 2105.90
  4869.7 2101.01  4932.4 2096.93  4990.0 2088.87  5000.1 2088.90  5000.9 2086.89
  5001.4 2086.39  5026.6 2086.89  5029.6 2088.37  5035.3 2088.09  5051.2 2090.94
  5057.7 2093.90  5067.0 2107.82  5072.8 2110.19  5080.7 2121.07  5088.6 2129.65
  5094.4 2131.57  5103.7 2138.44  5110.2 2140.77  5131.8 2140.71  5175.0 2145.03
  5265.0 2151.71  5271.5 2153.49  5307.8 2155.69  5389.5 2158.68  5403.2 2160.26
#Mann=4,-1,0
  4298.3     0.1       0  5000.9    0.05       0  5026.6     0.1       0
  5307.8    0.07       0
Bank Sta=5000.9,5026.6
Exp/Cntr=0.3,0.1

Type RM Length L Ch R = 1,3823,566,566,566
BEGIN DESCRIPTION:
Stream0095 7.0
END DESCRIPTION:
XS GIS Cut Line= 3
      1783275.01     13921725.01      1783725.00     13922025.00
      1784074.97     13922224.98
#Sta/Elev= 30
  4454.8 2114.62  4519.4 2111.36  4534.4 2111.35  4555.4 2109.44  4663.6 2104.51
  4771.8 2100.99  4837.9 2099.80  4864.9 2097.61  4901.0 2096.19  4937.0 2092.26
  4952.1 2089.24  4979.8 2086.33  4980.3 2085.83  5005.5 2086.33  5030.9 2090.12
  5041.0 2090.78  5053.2 2095.93  5068.3 2113.20  5076.2 2124.30  5082.0 2129.67
  5084.2 2135.05  5089.9 2138.82  5099.3 2141.57  5121.6 2144.35  5143.2 2148.64
  5164.8 2149.96  5192.1 2153.93  5208.0 2154.35  5233.5 2157.36  5398.7 2164.60
#Mann=4,-1,0
  4454.8     0.1       0  4979.8    0.05       0  5005.5     0.1       0
  5233.5    0.07       0
Bank Sta=4979.8,5005.5
Exp/Cntr=0.3,0.1

Type RM Length L Ch R = 1,3257,513,513,513
BEGIN DESCRIPTION:
Stream0095 6.0
END DESCRIPTION:
XS GIS Cut Line= 3
      1782625.03     13922325.00      1783425.00     13922475.00
      1783824.98     13922574.99
#Sta/Elev= 30
  4186.1 2141.44  4236.9 2138.14  4328.5 2128.95  4501.5 2118.76  4562.5 2113.04
  4595.6 2108.96  4623.6 2103.07  4633.7 2101.99  4648.2 2098.05  4684.6 2096.67
  4725.3 2097.40  4786.4 2096.13  4827.1 2093.93  4863.5 2090.59  4908.4 2090.19
  4949.1 2087.97  4979.7 2089.57  4984.6 2086.53  4985.1 2086.03  5010.3 2086.53
  5018.1 2086.65  5059.3 2092.50  5092.8 2102.48  5146.9 2115.07  5175.2 2122.91
  5206.2 2132.65  5237.1 2144.20  5278.3 2155.10  5389.1 2168.07  5412.3 2169.65
#Mann=3,-1,0
  4186.1     0.1       0  4984.6    0.05       0  5010.3     0.1       0
Bank Sta=4984.6,5010.3
Exp/Cntr=0.3,0.1

Type RM Length L Ch R = 1,2744,553,553,553
BEGIN DESCRIPTION:
Stream0095 5.0
END DESCRIPTION:
XS GIS Cut Line= 3
      1782475.02     13922325.01      1783225.00     13922925.00
      1783625.04     13922975.01
#Sta/Elev= 30
  4044.1 2152.28  4094.5 2150.07  4144.1 2144.46  4214.6 2141.32  4307.4 2130.55
  4449.9 2122.06  4534.7 2114.22  4598.7 2105.18  4620.4 2094.67  4627.6 2092.92
  4648.4 2090.40  4656.4 2091.40  4685.1 2087.03  4685.6 2086.53  4710.9 2087.03
  4712.4 2089.39  4798.8 2091.57  4976.5 2089.68  5034.8 2092.91  5065.0 2098.43
  5145.6 2100.31  5165.8 2103.32  5208.6 2114.36  5236.3 2125.14  5266.6 2132.56
  5284.2 2140.79  5289.2 2140.41  5306.9 2146.08  5364.8 2153.81  5407.7 2156.75
#Mann=3,-1,0
  4044.1     0.1       0  4685.1    0.05       0  4710.9     0.1       0
Bank Sta=4685.1,4710.9
Exp/Cntr=0.3,0.1

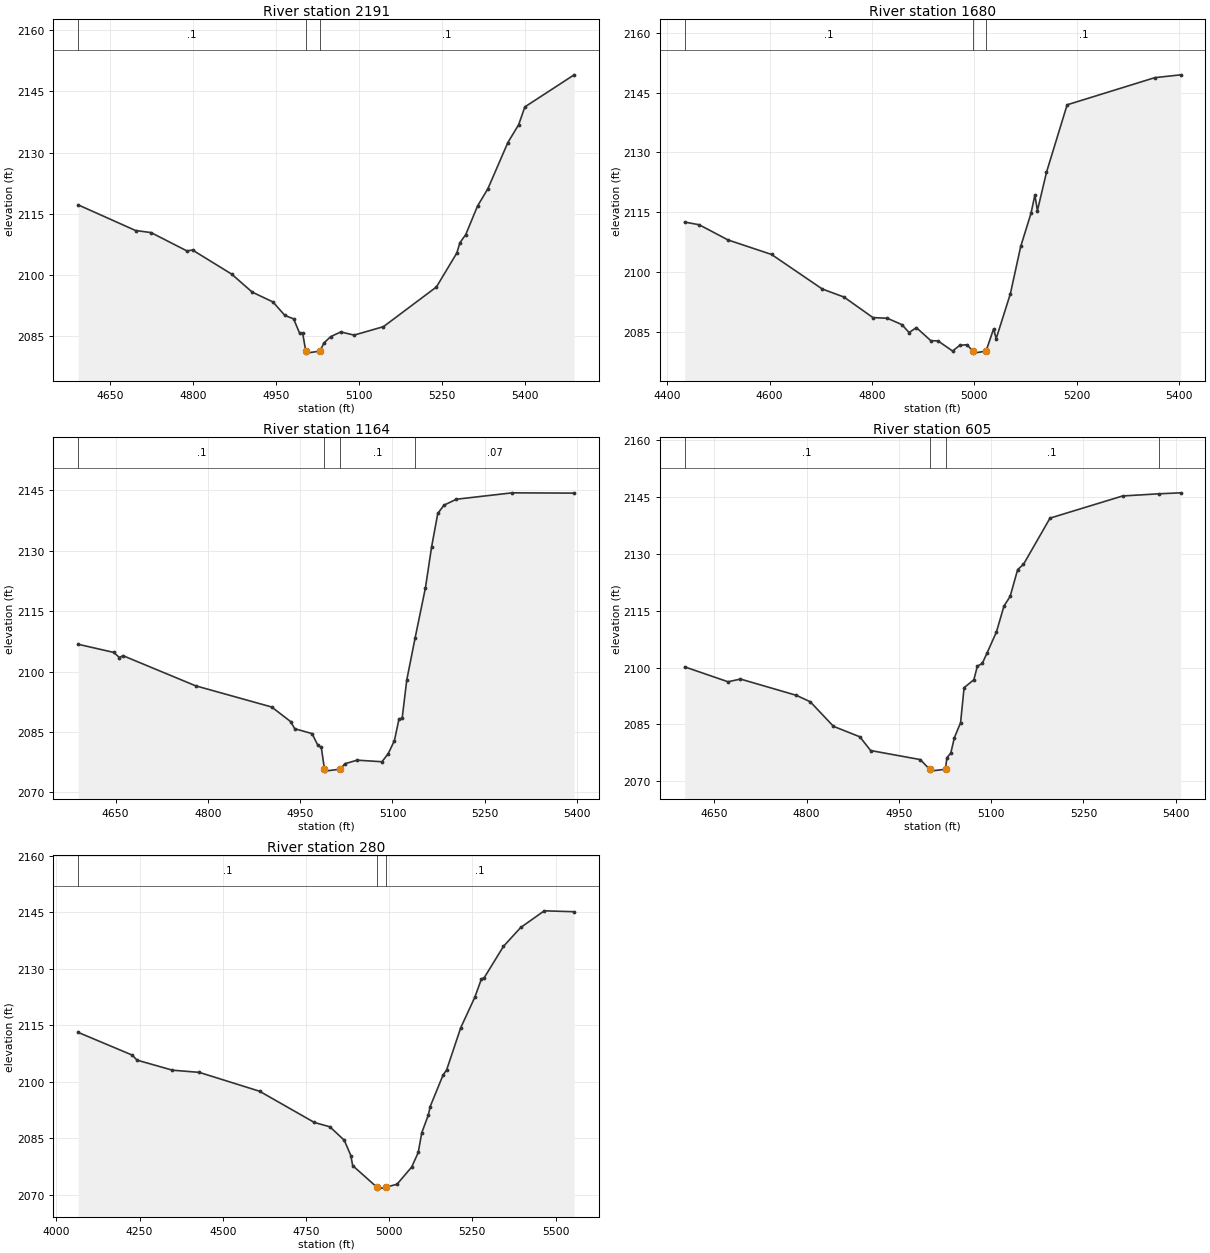
Type RM Length L Ch R = 1,2191,511,511,511
BEGIN DESCRIPTION:
Stream0095 4.0
END DESCRIPTION:
XS GIS Cut Line= 3
      1782675.01     13922875.02      1782875.00     13923225.00
      1783339.40     13923391.71
#Sta/Elev= 30
  4592.8 2117.21  4696.4 2110.94  4724.5 2110.43  4789.3 2105.94  4799.4 2106.16
  4869.9 2100.29  4907.3 2095.86  4944.8 2093.45  4966.4 2090.15  4982.2 2089.30
  4993.0 2085.80  4998.5 2085.80  5004.2 2081.42  5004.7 2080.92  5030.0 2081.42
  5036.7 2083.36  5049.0 2084.94  5067.4 2086.11  5091.5 2085.33  5144.6 2087.40
  5240.3 2097.11  5277.2 2105.43  5282.8 2107.95  5293.4 2109.96  5314.6 2116.92
  5333.4 2121.18  5369.5 2132.48  5389.0 2136.85  5400.2 2141.20  5489.3 2149.05
#Mann=3,-1,0
  4592.8     0.1       0  5004.2    0.05       0  5030.0     0.1       0
Bank Sta=5004.2,5030
Exp/Cntr=0.3,0.1

Type RM Length L Ch R = 1,1680,516,516,516
BEGIN DESCRIPTION:
Stream0095 3.0
END DESCRIPTION:
XS GIS Cut Line= 3
      1782374.99     13923274.99      1782775.00     13923675.00
      1783174.99     13923625.00
#Sta/Elev= 30
  4434.3 2112.48  4462.6 2111.81  4519.2 2107.98  4604.0 2104.35  4703.0 2095.68
  4745.4 2093.66  4802.0 2088.50  4830.3 2088.32  4858.6 2086.73  4872.7 2084.74
  4886.9 2085.98  4915.1 2082.70  4929.3 2082.63  4957.6 2080.10  4971.7 2081.53
  4985.9 2081.68  4997.2 2080.07  4997.7 2079.57  5023.0 2080.07  5037.8 2085.67
  5042.8 2083.21  5070.5 2094.47  5090.7 2106.35  5110.9 2114.71  5118.4 2119.28
  5123.4 2115.37  5141.1 2124.99  5181.4 2141.93  5352.7 2148.75  5403.1 2149.46
#Mann=3,-1,0
  4434.3     0.1       0  4997.2    0.05       0  5023.0     0.1       0
Bank Sta=4997.2,5023
Exp/Cntr=0.3,0.1

Type RM Length L Ch R = 1,1164,559,559,559
BEGIN DESCRIPTION:
Stream0095 2.0
END DESCRIPTION:
XS GIS Cut Line= 3
      1782174.99     13923474.99      1782375.00     13923825.00
      1782325.01     13924224.96
#Sta/Elev= 30
  4589.1 2106.77  4646.7 2104.76  4656.1 2103.49  4661.8 2103.95  4779.9 2096.47
  4903.7 2091.20  4934.6 2087.56  4941.1 2085.81  4969.2 2084.61  4978.6 2081.73
  4984.3 2081.16  4989.4 2075.79  4989.9 2075.29  5015.3 2075.79  5022.5 2077.12
  5042.6 2078.01  5082.9 2077.62  5093.0 2079.62  5103.1 2082.84  5110.6 2088.27
  5115.7 2088.42  5123.2 2097.91  5136.9 2108.45  5153.5 2120.74  5163.6 2130.97
  5173.6 2139.24  5183.7 2141.30  5203.9 2142.77  5294.6 2144.36  5395.3 2144.29
#Mann=4,-1,0
  4589.1     0.1       0  4989.4    0.05       0  5015.3     0.1       0
  5136.9    0.07       0
Bank Sta=4989.4,5015.3
Exp/Cntr=0.3,0.1

Type RM Length L Ch R = 1,605,325,325,325
BEGIN DESCRIPTION:
Stream0095 1.0
END DESCRIPTION:
XS GIS Cut Line= 3
      1781925.00     13923625.00      1781875.00     13924025.00
      1782224.98     13924224.99
#Sta/Elev= 30
  4601.8 2100.20  4672.3 2096.26  4692.5 2096.98  4783.2 2092.69  4805.9 2090.99
  4843.7 2084.49  4886.5 2081.73  4904.1 2078.10  4984.8 2075.71  4999.9 2073.16
  5000.4 2072.66  5025.8 2073.16  5028.0 2076.20  5034.4 2077.43  5040.2 2081.49
  5050.3 2085.44  5056.0 2094.70  5071.9 2096.80  5077.6 2100.39  5085.5 2101.09
  5093.5 2103.92  5108.6 2109.43  5120.8 2116.24  5130.9 2118.83  5143.1 2125.91
  5152.5 2127.26  5195.7 2139.49  5313.7 2145.34  5372.4 2145.91  5408.0 2146.17
#Mann=4,-1,0
  4601.8     0.1       0  4999.9    0.05       0  5025.8     0.1       0
  5372.4    0.07       0
Bank Sta=4999.9,5025.8
Exp/Cntr=0.3,0.1

Type RM Length L Ch R = 1,280,0,0,0
BEGIN DESCRIPTION:
Stream0095 0.0
END DESCRIPTION:
XS GIS Cut Line= 4
      1781599.86     13923153.52      1781512.52     13923922.94
      1781656.09     13924312.10      1781910.92     13924472.39
#Sta/Elev= 30
  4065.8 2113.07  4228.3 2107.04  4242.6 2105.71  4349.1 2103.04  4429.6 2102.46
  4610.8 2097.45  4775.3 2089.17  4822.1 2088.01  4865.4 2084.43  4885.0 2080.37
  4890.5 2077.72  4963.5 2071.97  4964.0 2071.47  4989.4 2071.97  5023.6 2072.76
  5067.8 2077.33  5087.5 2081.20  5098.2 2086.47  5118.0 2091.16  5123.3 2093.37
  5162.1 2101.76  5172.8 2103.11  5215.4 2114.35  5257.3 2122.36  5277.3 2127.23
  5285.9 2127.61  5343.6 2135.91  5395.4 2140.92  5466.3 2145.34  5556.0 2145.10
#Mann=3,-1,0
  4065.8     0.1       0  4963.5    0.05       0  4989.4     0.1       0
Bank Sta=4963.5,4989.4
Exp/Cntr=0.3,0.1

Chan Stop Cuts=-1