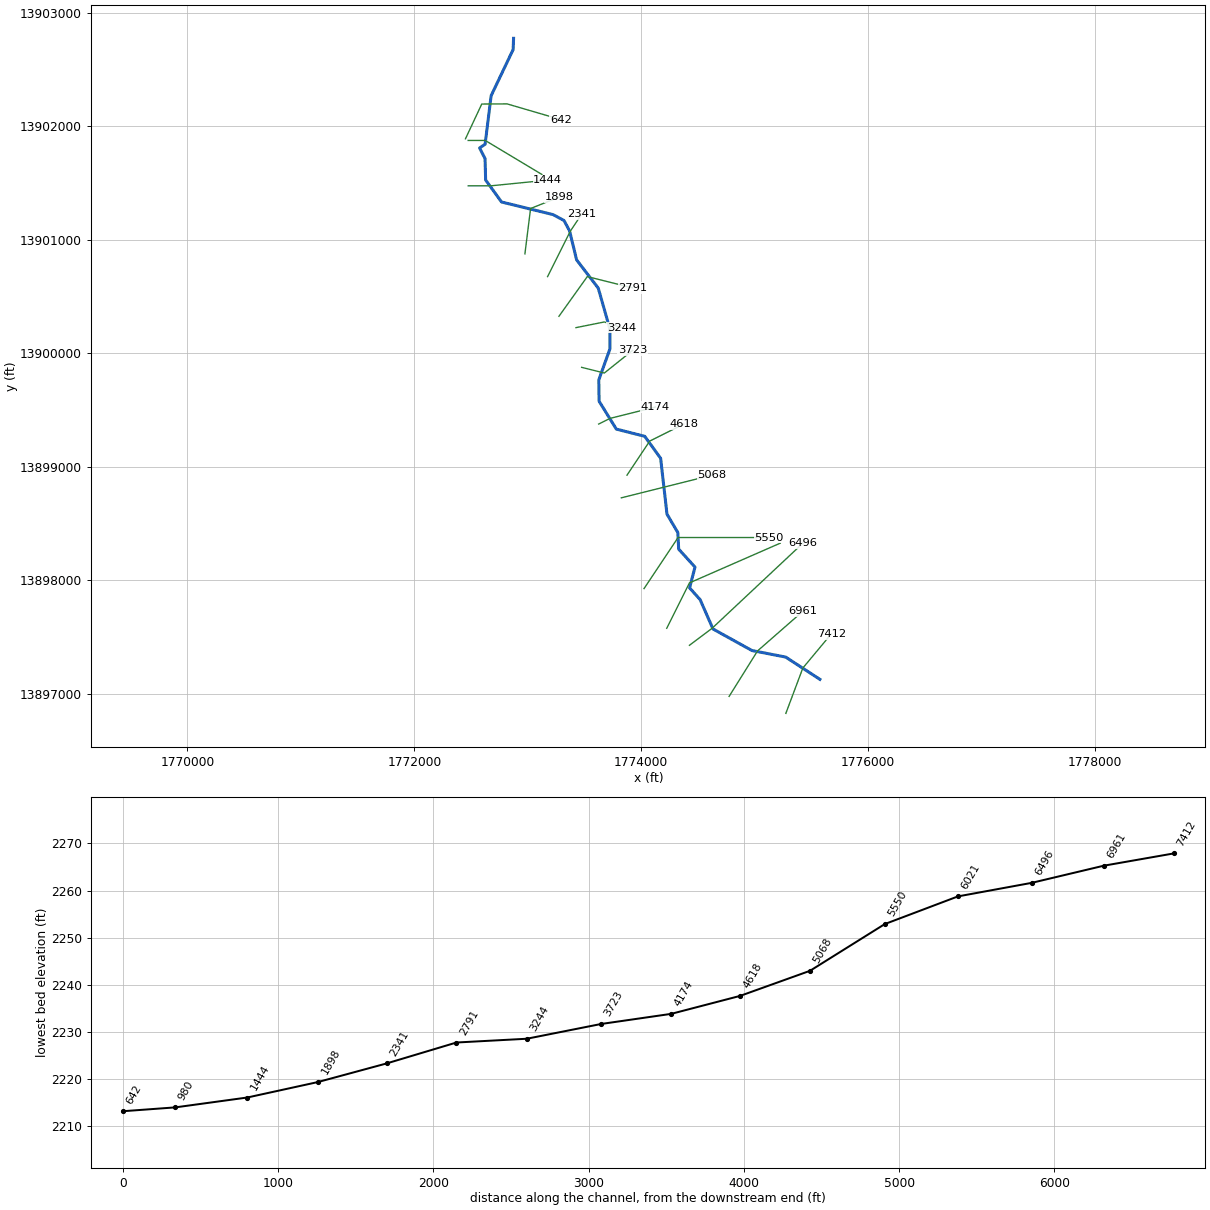
--- Stream0097.prj (project) ---

Proj Title=Stream0097 Base Level Engineering
Current Plan=p01
Default Exp/Contr=0.3,0.1
English Units
Geom File=g01
Flow File=f01
Plan File=p01
BEGIN DESCRIPTION:
Stream0097
END DESCRIPTION:

--- Stream0097.p01 (plan) ---

Plan Title=Multiple Run
Short Identifier=Multiple
Geom File=g01
Flow File=f01
Subcritical Flow
K Sum by GR= 0
Std Step Tol= 0.01
Critical Tol= 0.01
Num of Std Step Trials= 20
Max Error Tol= 0.3
Flow Tol Ratio= 0.001
Split Flow NTrial= 30
Split Flow Tol= 0.02
Split Flow Ratio= 0.02
Log Output Level= 0
Friction Slope Method= 1
Unsteady Friction Slope Method= 2
Unsteady Bridges Friction Slope Method= 1
Parabolic Critical Depth
Global Vel Dist=  1 , 1 , 1
Global Log Level= 0
CheckData=True
Encroach Param= -1, 0, 0, 0
BEGIN DESCRIPTION:
Multiple Run
END DESCRIPTION:

--- Stream0097.f01 (steady flow) ---

Flow Title=Multiple
Number of Profiles=7
Profile Names=10-year,25-year,50-year,1pct_min,100-year,1pct_plu,500-year
River Rch & RM= Stream0097,Reach-1,7412
    1434    2464    3448    2326    4640    9259    8319
River Rch & RM= Stream0097,Reach-1,1444
    2162    3805    5410    3705    7392   14748   13661
Boundary for River Rch & Prof#=Stream0097,Reach-1,1
Up Type=0
Dn Type=3
Dn Slope=0.005
Boundary for River Rch & Prof#=Stream0097,Reach-1,2
Up Type=0
Dn Type=3
Dn Slope=0.005
Boundary for River Rch & Prof#=Stream0097,Reach-1,3
Up Type=0
Dn Type=3
Dn Slope=0.005
Boundary for River Rch & Prof#=Stream0097,Reach-1,4
Up Type=0
Dn Type=3
Dn Slope=0.005
Boundary for River Rch & Prof#=Stream0097,Reach-1,5
Up Type=0
Dn Type=3
Dn Slope=0.005
Boundary for River Rch & Prof#=Stream0097,Reach-1,6
Up Type=0
Dn Type=3
Dn Slope=0.005
Boundary for River Rch & Prof#=Stream0097,Reach-1,7
Up Type=0
Dn Type=3
Dn Slope=0.005

--- Stream0097.g01 (geometry) ---

Geom Title=Existing Conditions

River Reach=Stream0097,Reach-1
Reach XY= 30
      1775575.00     13897125.00      1775273.44     13897321.24
      1774976.58     13897378.83      1774633.04     13897568.67
      1774519.46     13897827.42      1774426.63     13897931.04
      1774474.07     13898114.52      1774330.47     13898272.55
      1774322.75     13898419.07      1774227.24     13898580.93
      1774171.25     13899073.45      1774031.21     13899267.19
      1773780.61     13899330.59      1773628.75     13899576.55
      1773626.22     13899764.49      1773723.78     13900035.51
      1773723.78     13900214.49      1773621.38     13900573.50
      1773430.48     13900822.56      1773368.94     13901077.23
      1773319.42     13901169.42      1773223.44     13901221.19
      1772768.68     13901332.50      1772628.74     13901526.55
      1772623.75     13901714.52      1772575.53     13901808.86
      1772624.00     13901840.94      1772677.25     13902269.07
      1772871.37     13902676.50      1772875.00     13902775.00

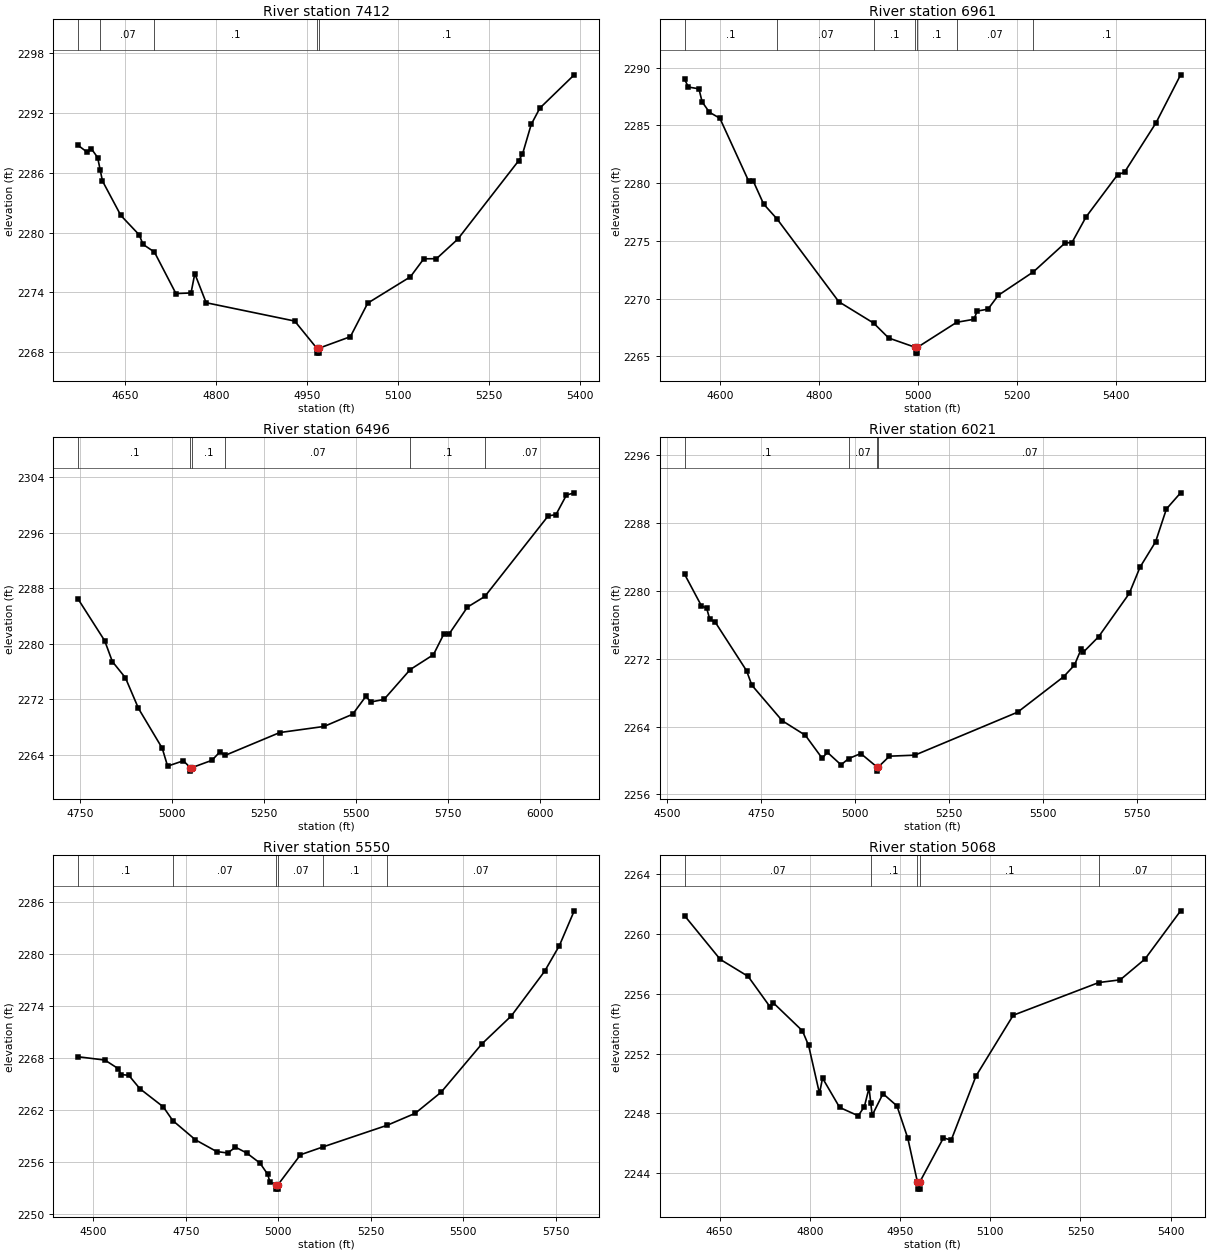
Type RM Length L Ch R = 1,7412,451,451,451
BEGIN DESCRIPTION:
Stream0097 15.0
END DESCRIPTION:
XS GIS Cut Line= 3
      1775275.00     13896825.00      1775425.00     13897225.00
      1775674.99     13897524.99
#Sta/Elev= 30
  4572.8 2288.74  4587.9 2288.05  4594.2 2288.43  4604.8 2287.53  4609.2 2286.23
  4612.8 2285.17  4643.1 2281.71  4673.4 2279.76  4679.6 2278.81  4698.4 2278.04
  4733.9 2273.87  4758.8 2273.93  4765.0 2275.87  4783.7 2272.95  4929.7 2271.11
  4966.0 2268.39  4966.2 2267.89  4969.7 2267.89  4970.0 2268.39  5021.5 2269.54
  5050.1 2272.91  5120.4 2275.55  5142.5 2277.36  5163.4 2277.37  5198.5 2279.33
  5298.7 2287.19  5305.2 2287.86  5319.6 2290.85  5333.9 2292.49  5390.5 2295.83
#Mann=5,-1,0
  4572.8     0.1       0  4609.2    0.07       0  4698.4     0.1       0
  4966.0    0.05       0  4970.0     0.1       0
Bank Sta=4966,4970
Exp/Cntr=0.3,0.1

Type RM Length L Ch R = 1,6961,465,465,465
BEGIN DESCRIPTION:
Stream0097 14.0
END DESCRIPTION:
XS GIS Cut Line= 3
      1774775.00     13896975.00      1775025.00     13897375.00
      1775424.99     13897724.99
#Sta/Elev= 30
  4528.3 2288.98  4536.0 2288.32  4557.2 2288.17  4563.7 2287.04  4578.4 2286.14
  4599.6 2285.62  4658.0 2280.16  4666.9 2280.20  4688.1 2278.19  4715.4 2276.89
  4840.2 2269.73  4910.6 2267.88  4941.0 2266.59  4995.0 2265.78  4995.3 2265.28
  4998.9 2265.28  4999.1 2265.78  5078.6 2267.95  5113.4 2268.21  5120.1 2268.92
  5141.9 2269.09  5162.8 2270.29  5233.8 2272.32  5297.6 2274.81  5311.8 2274.86
  5340.3 2277.08  5403.9 2280.72  5418.1 2280.95  5481.7 2285.22  5531.5 2289.38
#Mann=7,-1,0
  4528.3     0.1       0  4715.4    0.07       0  4910.6     0.1       0
  4995.0    0.05       0  4999.1     0.1       0  5078.6    0.07       0
  5233.8     0.1       0
Bank Sta=4995,4999.1
Exp/Cntr=0.3,0.1

Type RM Length L Ch R = 1,6496,475,475,475
BEGIN DESCRIPTION:
Stream0097 13.0
END DESCRIPTION:
XS GIS Cut Line= 3
      1774424.98     13897424.99      1774625.00     13897575.00
      1775424.99     13898324.99
#Sta/Elev= 30
  4745.4 2286.40  4817.3 2280.42  4838.1 2277.42  4873.5 2275.09  4909.0 2270.67
  4973.5 2264.93  4988.1 2262.35  5030.8 2263.12  5049.8 2262.13  5050.1 2261.63
  5053.9 2262.13  5108.5 2263.19  5130.0 2264.40  5144.2 2263.90  5292.6 2267.19
  5412.8 2268.07  5490.5 2269.83  5526.1 2272.39  5540.3 2271.60  5575.5 2271.96
  5646.8 2276.27  5709.8 2278.41  5738.1 2281.40  5752.3 2281.39  5802.1 2285.27
  5849.3 2286.80  6021.4 2298.42  6042.4 2298.59  6070.8 2301.41  6092.0 2301.74
#Mann=6,-1,0
  4745.4     0.1       0  5049.8    0.05       0  5053.9     0.1       0
  5144.2    0.07       0  5646.8     0.1       0  5849.3    0.07       0
Bank Sta=5049.8,5053.9
Exp/Cntr=0.3,0.1

Type RM Length L Ch R = 1,6021,471,471,471
BEGIN DESCRIPTION:
Stream0097 12.0
END DESCRIPTION:
XS GIS Cut Line= 3
      1774225.01     13897575.03      1774425.00     13897975.00
      1775225.00     13898325.00
#Sta/Elev= 30
  4546.8 2281.92  4591.5 2278.21  4605.5 2277.92  4613.9 2276.61  4627.8 2276.32
  4711.7 2270.57  4725.7 2268.87  4806.7 2264.68  4868.2 2262.97  4912.9 2260.27
  4926.9 2260.96  4963.2 2259.49  4983.2 2260.22  5015.8 2260.82  5058.5 2259.25
  5058.8 2258.75  5062.7 2259.25  5092.2 2260.51  5159.7 2260.63  5433.3 2265.69
  5555.7 2269.86  5584.6 2271.23  5602.5 2273.12  5608.0 2272.74  5648.9 2274.57
  5730.4 2279.66  5759.2 2282.76  5800.5 2285.74  5829.4 2289.61  5867.2 2291.51
#Mann=4,-1,0
  4546.8     0.1       0  4983.2    0.07       0  5058.5    0.05       0
  5062.7    0.07       0
Bank Sta=5058.5,5062.7
Exp/Cntr=0.3,0.1

Type RM Length L Ch R = 1,5550,482,482,482
BEGIN DESCRIPTION:
Stream0097 11.0
END DESCRIPTION:
XS GIS Cut Line= 3
      1774024.98     13897924.97      1774325.00     13898375.00
      1775125.03     13898375.00
#Sta/Elev= 30
  4458.8 2268.15  4530.9 2267.77  4567.0 2266.78  4574.5 2266.10  4595.5 2266.01
  4625.6 2264.46  4688.7 2262.37  4714.3 2260.79  4775.8 2258.56  4832.9 2257.21
  4863.0 2257.04  4884.0 2257.71  4914.0 2257.05  4950.1 2255.88  4971.1 2254.58
  4977.1 2253.67  4994.6 2253.37  4994.8 2252.87  4998.5 2252.87  4998.8 2253.37
  5059.7 2256.84  5121.0 2257.75  5293.9 2260.24  5369.7 2261.62  5439.7 2264.05
  5549.7 2269.62  5629.7 2272.87  5719.7 2278.02  5759.7 2280.99  5799.7 2285.00
#Mann=6,-1,0
  4458.8     0.1       0  4714.3    0.07       0  4994.6    0.05       0
  4998.8    0.07       0  5121.0     0.1       0  5293.9    0.07       0
Bank Sta=4994.6,4998.8
Exp/Cntr=0.3,0.1

Type RM Length L Ch R = 1,5068,450,450,450
BEGIN DESCRIPTION:
Stream0097 10.0
END DESCRIPTION:
XS GIS Cut Line= 3
      1773825.03     13898725.01      1774225.00     13898825.00
      1774625.01     13898925.00
#Sta/Elev= 30
  4591.9 2261.23  4651.1 2258.31  4697.5 2257.17  4733.6 2255.15  4738.8 2255.42
  4787.7 2253.53  4798.0 2252.55  4816.1 2249.34  4821.2 2250.36  4849.6 2248.40
  4880.5 2247.84  4890.8 2248.46  4898.5 2249.71  4901.4 2248.68  4903.7 2247.87
  4921.7 2249.32  4944.9 2248.50  4963.0 2246.33  4978.8 2243.43  4979.1 2242.93
  4982.9 2242.93  4983.2 2243.43  5022.2 2246.36  5035.1 2246.21  5076.3 2250.50
  5138.2 2254.57  5280.5 2256.76  5316.0 2256.94  5357.2 2258.33  5416.5 2261.56
#Mann=5,-1,0
  4591.9    0.07       0  4901.4     0.1       0  4978.8    0.05       0
  4983.2     0.1       0  5280.5    0.07       0
Bank Sta=4978.8,4983.2
Exp/Cntr=0.3,0.1

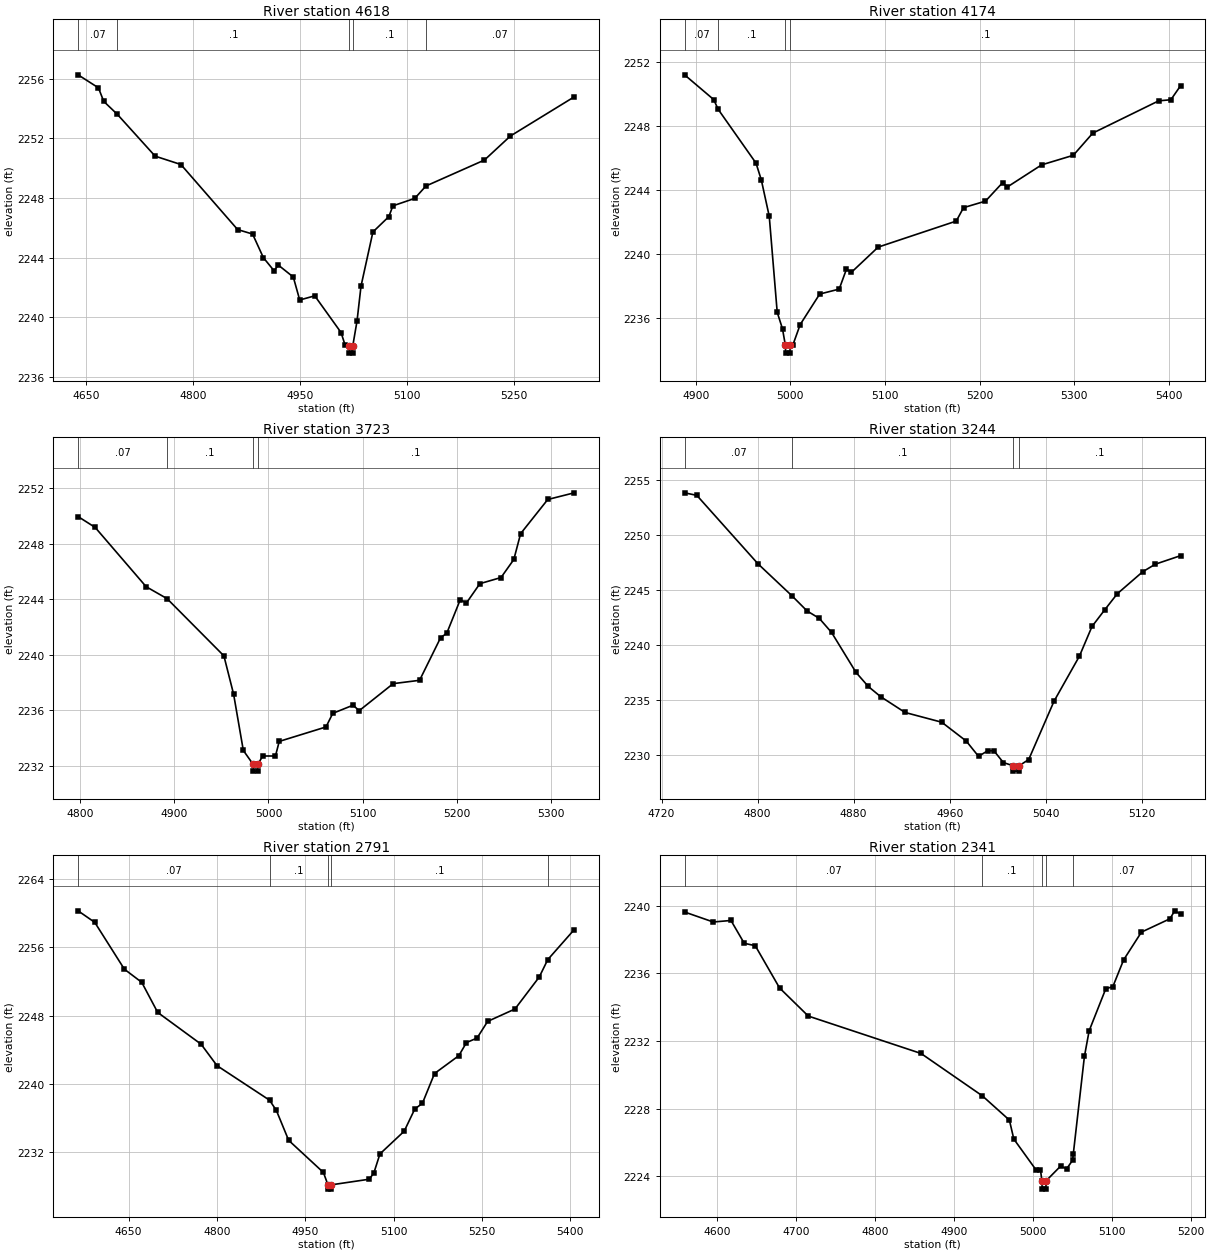
Type RM Length L Ch R = 1,4618,444,444,444
BEGIN DESCRIPTION:
Stream0097 9.0
END DESCRIPTION:
XS GIS Cut Line= 3
      1773875.02     13898925.03      1774075.00     13899225.00
      1774374.98     13899374.99
#Sta/Elev= 30
  4639.0 2256.25  4667.5 2255.38  4675.0 2254.47  4694.1 2253.60  4747.1 2250.80
  4783.2 2250.24  4862.8 2245.88  4883.8 2245.58  4898.9 2244.00  4913.9 2243.12
  4919.9 2243.50  4940.9 2242.70  4949.9 2241.16  4971.0 2241.44  5007.9 2238.98
  5013.5 2238.15  5019.3 2238.10  5019.7 2237.60  5024.0 2237.60  5024.4 2238.10
  5030.3 2239.75  5035.9 2242.09  5052.6 2245.72  5075.0 2246.75  5080.6 2247.47
  5111.3 2247.97  5127.0 2248.80  5209.1 2250.54  5245.5 2252.15  5334.9 2254.77
#Mann=5,-1,0
  4639.0    0.07       0  4694.1     0.1       0  5019.3    0.05       0
  5024.4     0.1       0  5127.0    0.07       0
Bank Sta=5019.3,5024.4
Exp/Cntr=0.3,0.1

Type RM Length L Ch R = 1,4174,451,451,451
BEGIN DESCRIPTION:
Stream0097 8.0
END DESCRIPTION:
XS GIS Cut Line= 3
      1773624.96     13899374.98      1773725.00     13899425.00
      1774125.04     13899525.01
#Sta/Elev= 30
  4888.2 2251.21  4919.0 2249.66  4923.7 2249.05  4963.7 2245.68  4969.3 2244.63
  4977.7 2242.35  4986.1 2236.34  4991.7 2235.30  4994.7 2234.28  4995.1 2233.78
  4999.5 2233.78  4999.9 2234.28  5002.6 2234.28  5010.4 2235.57  5031.0 2237.48
  5051.6 2237.79  5059.3 2239.04  5064.5 2238.84  5092.8 2240.42  5175.3 2242.05
  5183.0 2242.89  5206.2 2243.30  5224.2 2244.45  5229.4 2244.19  5265.5 2245.57
  5299.0 2246.17  5319.6 2247.56  5389.2 2249.58  5402.1 2249.65  5412.4 2250.53
#Mann=4,-1,0
  4888.2    0.07       0  4923.7     0.1       0  4994.7    0.05       0
  4999.9     0.1       0
Bank Sta=4994.7,4999.9
Exp/Cntr=0.3,0.1

Type RM Length L Ch R = 1,3723,479,479,479
BEGIN DESCRIPTION:
Stream0097 7.0
END DESCRIPTION:
XS GIS Cut Line= 3
      1773474.96     13899875.01      1773675.00     13899825.00
      1773924.96     13900024.97
#Sta/Elev= 30
  4798.0 2249.96  4816.1 2249.18  4870.2 2244.91  4892.4 2244.05  4952.7 2239.93
  4963.0 2237.17  4973.3 2233.12  4983.6 2232.13  4984.0 2231.63  4988.4 2231.63
  4988.8 2232.13  4993.9 2232.72  5007.4 2232.72  5011.4 2233.77  5061.0 2234.81
  5068.2 2235.79  5089.8 2236.38  5096.2 2235.98  5132.3 2237.93  5160.3 2238.17
  5182.7 2241.25  5189.1 2241.55  5203.5 2243.98  5209.9 2243.73  5224.3 2245.13
  5246.7 2245.57  5260.3 2246.87  5267.5 2248.73  5296.3 2251.19  5324.3 2251.67
#Mann=4,-1,0
  4798.0    0.07       0  4892.4     0.1       0  4983.6    0.05       0
  4988.8     0.1       0
Bank Sta=4983.6,4988.8
Exp/Cntr=0.3,0.1

Type RM Length L Ch R = 1,3244,453,453,453
BEGIN DESCRIPTION:
Stream0097 6.0
END DESCRIPTION:
XS GIS Cut Line= 3
      1773424.95     13900224.99      1773675.00     13900275.00
      1773824.99     13900225.00
#Sta/Elev= 30
  4739.2 2253.87  4749.4 2253.64  4800.4 2247.39  4828.9 2244.45  4841.2 2243.10
  4851.4 2242.42  4861.6 2241.14  4882.0 2237.49  4892.2 2236.21  4902.4 2235.29
  4922.8 2233.84  4953.4 2232.95  4973.8 2231.23  4984.0 2229.84  4991.7 2230.35
  4996.8 2230.35  5004.7 2229.27  5012.6 2228.99  5013.0 2228.49  5017.5 2228.49
  5018.0 2228.99  5025.8 2229.55  5046.9 2234.87  5068.0 2238.97  5078.5 2241.68
  5089.1 2243.20  5099.6 2244.67  5120.7 2246.67  5131.2 2247.36  5152.3 2248.14
#Mann=4,-1,0
  4739.2    0.07       0  4828.9     0.1       0  5012.6    0.05       0
  5018.0     0.1       0
Bank Sta=5012.6,5018
Exp/Cntr=0.3,0.1

Type RM Length L Ch R = 1,2791,450,450,450
BEGIN DESCRIPTION:
Stream0097 5.0
END DESCRIPTION:
XS GIS Cut Line= 3
      1773275.01     13900325.01      1773525.00     13900675.00
      1773924.98     13900575.00
#Sta/Elev= 30
  4564.3 2260.26  4592.6 2258.91  4642.9 2253.43  4672.4 2251.89  4699.5 2248.37
  4773.2 2244.65  4800.2 2242.14  4889.4 2238.10  4901.0 2236.90  4921.9 2233.40
  4980.9 2229.64  4988.6 2228.19  4989.1 2227.69  4993.6 2227.69  4994.0 2228.19
  5058.8 2228.85  5066.6 2229.59  5076.9 2231.81  5118.1 2234.47  5136.1 2237.07
  5149.0 2237.73  5169.6 2241.22  5210.9 2243.31  5223.8 2244.84  5241.8 2245.37
  5259.8 2247.32  5306.2 2248.77  5347.4 2252.51  5361.9 2254.55  5406.7 2258.05
#Mann=5,-1,0
  4564.3    0.07       0  4889.4     0.1       0  4988.6    0.05       0
  4994.0     0.1       0  5361.9    0.07       0
Bank Sta=4988.6,4994
Exp/Cntr=0.3,0.1

Type RM Length L Ch R = 1,2341,443,443,443
BEGIN DESCRIPTION:
Stream0097 4.0
END DESCRIPTION:
XS GIS Cut Line= 3
      1773175.01     13900675.01      1773375.00     13901075.00
      1773475.01     13901225.02
#Sta/Elev= 30
  4559.1 2239.62  4595.4 2239.03  4617.8 2239.12  4634.6 2237.77  4648.5 2237.63
  4679.3 2235.13  4715.6 2233.47  4858.2 2231.26  4935.9 2228.75  4970.0 2227.32
  4975.6 2226.20  5003.5 2224.39  5009.3 2224.39  5011.1 2223.74  5011.5 2223.24
  5016.1 2223.24  5016.6 2223.74  5034.8 2224.60  5042.4 2224.44  5049.9 2224.94
  5050.8 2225.30  5064.9 2231.08  5070.9 2232.60  5091.9 2235.08  5100.9 2235.21
  5114.5 2236.79  5137.0 2238.43  5173.1 2239.22  5179.1 2239.69  5186.6 2239.50
#Mann=5,-1,0
  4559.1    0.07       0  4935.9     0.1       0  5011.1    0.05       0
  5016.6     0.1       0  5050.8    0.07       0
Bank Sta=5011.1,5016.6
Exp/Cntr=0.3,0.1

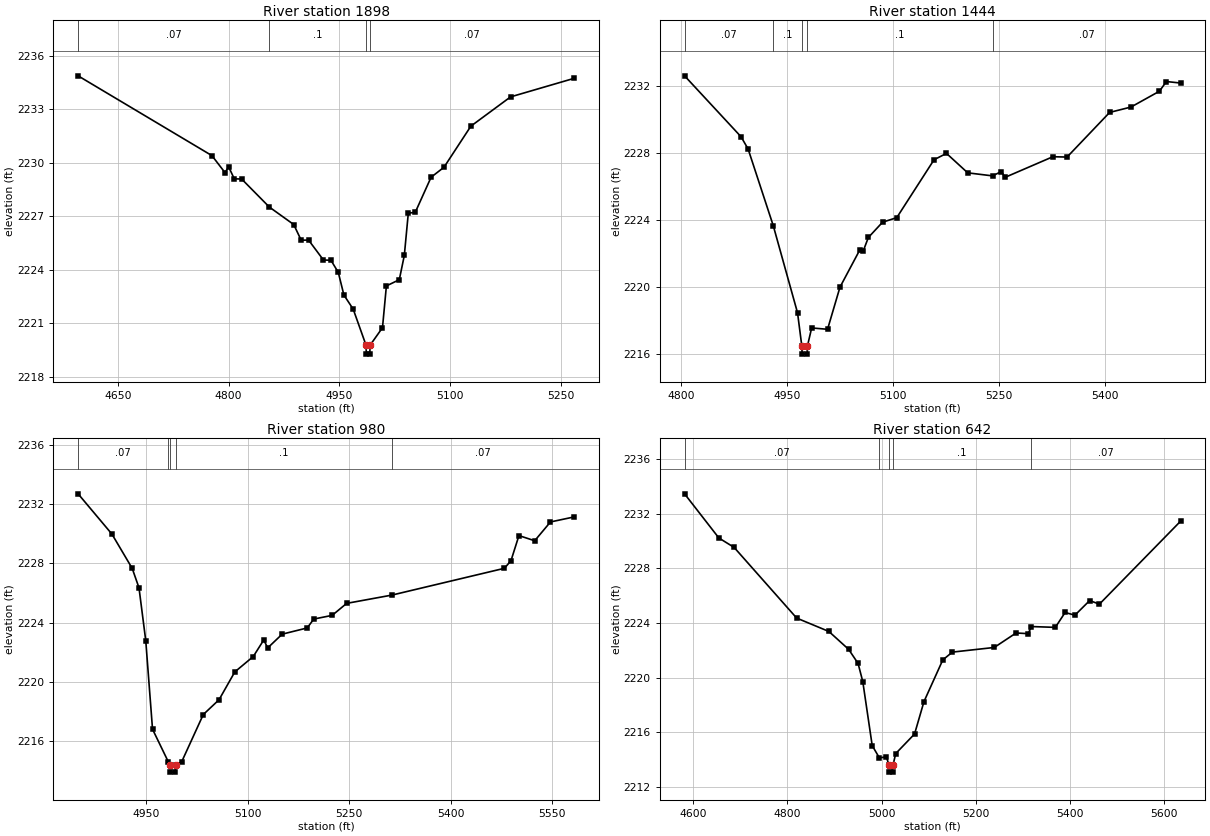
Type RM Length L Ch R = 1,1898,454,454,454
BEGIN DESCRIPTION:
Stream0097 3.0
END DESCRIPTION:
XS GIS Cut Line= 3
      1772975.00     13900874.98      1773025.00     13901275.00
      1773275.01     13901375.00
#Sta/Elev= 30
  4596.0 2234.87  4777.4 2230.40  4795.1 2229.45  4800.1 2229.77  4807.7 2229.10
  4817.7 2229.09  4855.2 2227.52  4888.3 2226.54  4898.4 2225.66  4908.4 2225.67
  4928.6 2224.55  4938.7 2224.54  4948.7 2223.86  4956.3 2222.59  4968.9 2221.80
  4986.3 2219.78  4986.7 2219.28  4991.4 2219.28  4991.8 2219.78  5008.6 2220.76
  5013.9 2223.10  5031.4 2223.45  5038.2 2224.81  5043.6 2227.18  5053.0 2227.22
  5074.5 2229.19  5092.0 2229.75  5128.4 2232.05  5182.2 2233.69  5268.4 2234.73
#Mann=4,-1,0
  4596.0    0.07       0  4855.2     0.1       0  4986.3    0.05       0
  4991.8    0.07       0
Bank Sta=4986.3,4991.8
Exp/Cntr=0.3,0.1

Type RM Length L Ch R = 1,1444,464,464,464
BEGIN DESCRIPTION:
Stream0097 2.0
END DESCRIPTION:
XS GIS Cut Line= 3
      1772474.98     13901475.00      1772675.00     13901475.00
      1773174.98     13901525.00
#Sta/Elev= 30
  4804.9 2232.58  4884.9 2228.95  4894.9 2228.22  4930.6 2223.64  4964.9 2218.46
  4970.9 2216.50  4971.4 2216.00  4978.5 2216.00  4979.0 2216.50  4984.9 2217.56
  5007.4 2217.48  5025.0 2219.99  5052.7 2222.18  5057.7 2222.12  5065.2 2222.95
  5085.3 2223.86  5105.4 2224.13  5158.2 2227.58  5175.8 2227.96  5205.9 2226.80
  5241.0 2226.62  5253.7 2226.88  5258.7 2226.53  5326.5 2227.76  5346.6 2227.74
  5406.9 2230.40  5437.1 2230.72  5477.3 2231.66  5487.3 2232.24  5507.4 2232.15
#Mann=5,-1,0
  4804.9    0.07       0  4930.6     0.1       0  4970.9    0.05       0
  4979.0     0.1       0  5241.0    0.07       0
Bank Sta=4970.9,4979
Exp/Cntr=0.3,0.1

Type RM Length L Ch R = 1,980,338,338,338
BEGIN DESCRIPTION:
Stream0097 1.0
END DESCRIPTION:
XS GIS Cut Line= 3
      1772474.98     13901875.00      1772625.00     13901875.00
      1773124.99     13901575.01
#Sta/Elev= 30
  4849.4 2232.70  4899.4 2229.98  4929.4 2227.66  4939.4 2226.35  4949.4 2222.78
  4959.4 2216.80  4982.9 2214.58  4985.4 2214.40  4985.9 2213.90  4993.0 2213.90
  4993.5 2214.40  5002.3 2214.58  5034.4 2217.79  5057.7 2218.79  5081.0 2220.67
  5108.3 2221.71  5123.8 2222.83  5129.6 2222.29  5151.0 2223.22  5188.0 2223.64
  5197.7 2224.24  5224.9 2224.49  5246.3 2225.30  5313.2 2225.86  5479.5 2227.67
  5489.2 2228.19  5500.9 2229.88  5524.2 2229.53  5547.5 2230.80  5582.5 2231.14
#Mann=5,-1,0
  4849.4    0.07       0  4982.9     0.1       0  4985.4    0.05       0
  4993.5     0.1       0  5313.2    0.07       0
Bank Sta=4985.4,4993.5
Exp/Cntr=0.3,0.1

Type RM Length L Ch R = 1,642,0,0,0
BEGIN DESCRIPTION:
Stream0097 0.0
END DESCRIPTION:
XS GIS Cut Line= 4
      1772451.09     13901889.63      1772594.66     13902195.98
      1772817.88     13902197.17      1773290.55     13902058.99
#Sta/Elev= 30
  4581.3 2233.44  4654.2 2230.21  4686.6 2229.52  4819.5 2224.35  4888.0 2223.37
  4930.0 2222.06  4950.0 2221.03  4960.0 2219.70  4980.0 2215.02  4995.3 2214.12
  5010.0 2214.20  5015.9 2213.58  5016.4 2213.08  5023.6 2213.08  5024.1 2213.58
  5030.0 2214.44  5070.0 2215.87  5090.0 2218.24  5130.0 2221.29  5150.3 2221.86
  5239.3 2222.20  5285.7 2223.26  5311.4 2223.21  5318.4 2223.73  5369.1 2223.67
  5389.9 2224.76  5410.7 2224.56  5442.0 2225.63  5462.8 2225.37  5635.3 2231.44
#Mann=5,-1,0
  4581.3    0.07       0  4995.3     0.1       0  5015.9    0.05       0
  5024.1     0.1       0  5318.4    0.07       0
Bank Sta=5015.9,5024.1
Exp/Cntr=0.3,0.1

Chan Stop Cuts=-1