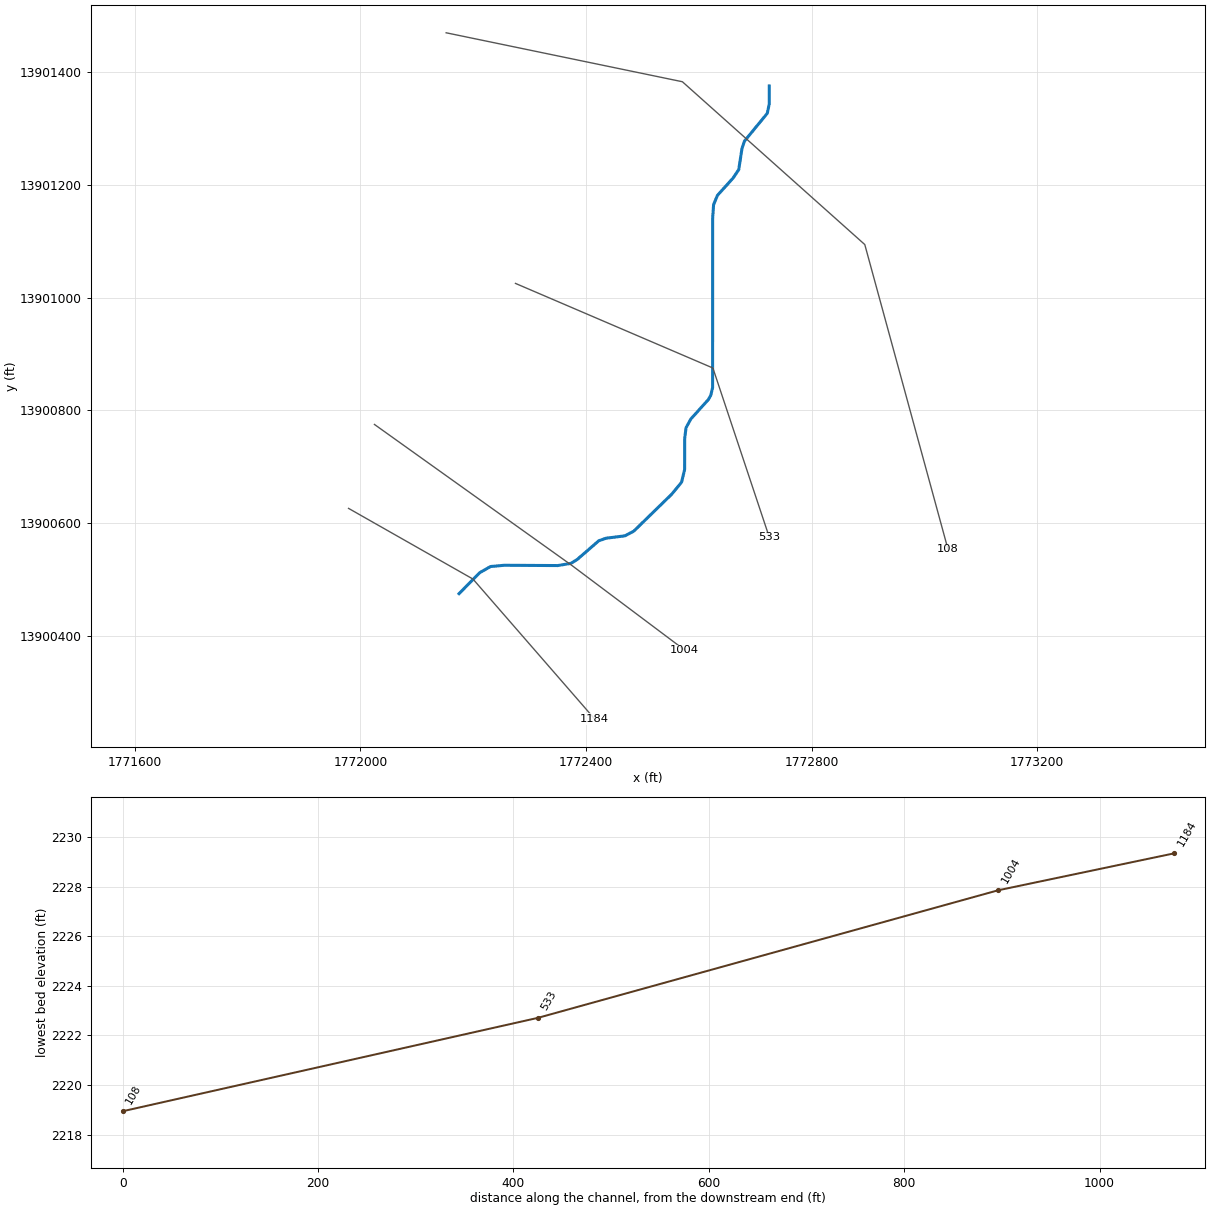
--- Stream0098.prj (project) ---

Proj Title=Stream0098 Base Level Engineering
Current Plan=p01
Default Exp/Contr=0.3,0.1
English Units
Geom File=g01
Flow File=f01
Plan File=p01
BEGIN DESCRIPTION:
Stream0098
END DESCRIPTION:

--- Stream0098.p01 (plan) ---

Plan Title=Multiple Run
Short Identifier=Multiple
Geom File=g01
Flow File=f01
Subcritical Flow
K Sum by GR= 0
Std Step Tol= 0.01
Critical Tol= 0.01
Num of Std Step Trials= 20
Max Error Tol= 0.3
Flow Tol Ratio= 0.001
Split Flow NTrial= 30
Split Flow Tol= 0.02
Split Flow Ratio= 0.02
Log Output Level= 0
Friction Slope Method= 1
Unsteady Friction Slope Method= 2
Unsteady Bridges Friction Slope Method= 1
Parabolic Critical Depth
Global Vel Dist=  1 , 1 , 1
Global Log Level= 0
CheckData=True
Encroach Param= -1, 0, 0, 0
BEGIN DESCRIPTION:
Multiple Run
END DESCRIPTION:

--- Stream0098.f01 (steady flow) ---

Flow Title=Multiple
Number of Profiles=7
Profile Names=10-year,25-year,50-year,1pct_min,100-year,1pct_plu,500-year
River Rch & RM= Stream0098,Reach-1,1184
    1000    1687    2331    1556    3104    6193    5441
Boundary for River Rch & Prof#=Stream0098,Reach-1,1
Up Type=0
Dn Type=3
Dn Slope=0.005
Boundary for River Rch & Prof#=Stream0098,Reach-1,2
Up Type=0
Dn Type=3
Dn Slope=0.005
Boundary for River Rch & Prof#=Stream0098,Reach-1,3
Up Type=0
Dn Type=3
Dn Slope=0.005
Boundary for River Rch & Prof#=Stream0098,Reach-1,4
Up Type=0
Dn Type=3
Dn Slope=0.005
Boundary for River Rch & Prof#=Stream0098,Reach-1,5
Up Type=0
Dn Type=3
Dn Slope=0.005
Boundary for River Rch & Prof#=Stream0098,Reach-1,6
Up Type=0
Dn Type=3
Dn Slope=0.005
Boundary for River Rch & Prof#=Stream0098,Reach-1,7
Up Type=0
Dn Type=3
Dn Slope=0.005

--- Stream0098.g01 (geometry) ---

Geom Title=Existing Conditions

River Reach=Stream0098,Reach-1
Reach XY= 30
      1772175.00     13900475.00      1772211.50     13900512.08
      1772230.79     13900523.09      1772254.87     13900525.32
      1772350.08     13900524.81      1772373.45     13900528.75
      1772384.67     13900535.80      1772422.83     13900568.86
      1772435.71     13900573.28      1772468.98     13900577.49
      1772484.71     13900585.75      1772552.14     13900651.43
      1772569.48     13900672.56      1772574.88     13900695.05
      1772575.01     13900750.00      1772577.36     13900769.02
      1772585.90     13900784.63      1772616.86     13900818.94
      1772621.22     13900826.56      1772624.48     13900840.22
      1772624.56     13901140.18      1772626.20     13901164.50
      1772633.09     13901181.08      1772660.96     13901211.96
      1772670.83     13901226.73      1772676.61     13901264.33
      1772680.95     13901277.25      1772721.40     13901326.49
      1772724.90     13901343.19      1772725.00     13901375.00

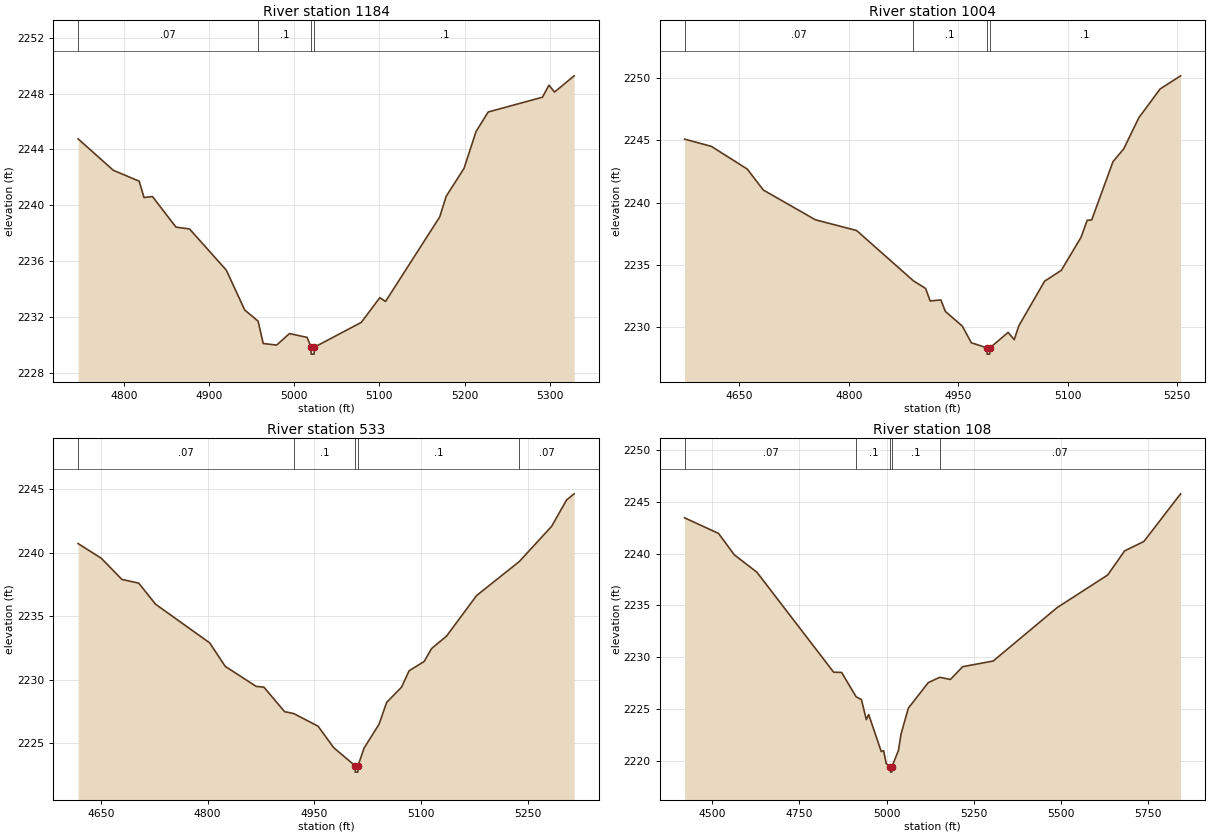
Type RM Length L Ch R = 1,1184,180,180,180
BEGIN DESCRIPTION:
Stream0098 3.0
END DESCRIPTION:
XS GIS Cut Line= 3
      1771979.12     13900626.20      1772199.71     13900500.88
      1772415.34     13900252.93
#Sta/Elev= 30
  4746.3 2244.76  4787.6 2242.51  4818.0 2241.73  4823.7 2240.56  4833.6 2240.63
  4861.2 2238.44  4877.1 2238.31  4920.3 2235.36  4941.9 2232.51  4957.6 2231.71
  4963.6 2230.11  4979.4 2230.00  4994.4 2230.82  5015.1 2230.55  5019.7 2229.85
  5019.9 2229.35  5023.4 2229.35  5023.7 2229.85  5078.7 2231.62  5100.5 2233.39
  5107.2 2233.12  5170.8 2239.17  5178.4 2240.65  5199.3 2242.64  5213.5 2245.29
  5227.7 2246.68  5291.4 2247.74  5299.0 2248.60  5305.6 2248.11  5328.6 2249.27
#Mann=4,-1,0
  4746.3    0.07       0  4957.6     0.1       0  5019.7    0.05       0
  5023.7     0.1       0
Bank Sta=5019.7,5023.7
Exp/Cntr=0.3,0.1

Type RM Length L Ch R = 1,1004,471,471,471
BEGIN DESCRIPTION:
Stream0098 2.0
END DESCRIPTION:
XS GIS Cut Line= 3
      1772025.03     13900774.98      1772375.00     13900525.00
      1772575.02     13900374.99
#Sta/Elev= 30
  4574.9 2245.08  4611.7 2244.50  4660.9 2242.68  4683.0 2241.00  4754.3 2238.62
  4810.8 2237.76  4888.7 2233.73  4905.4 2233.12  4911.6 2232.12  4926.3 2232.20
  4932.5 2231.28  4955.8 2230.10  4968.1 2228.77  4989.5 2228.36  4989.7 2227.86
  4993.2 2227.86  4993.5 2228.36  5018.5 2229.60  5026.9 2229.02  5033.1 2230.12
  5068.5 2233.70  5091.4 2234.57  5118.5 2237.22  5126.9 2238.58  5133.1 2238.61
  5162.3 2243.28  5176.9 2244.29  5197.7 2246.79  5226.9 2249.10  5255.0 2250.15
#Mann=4,-1,0
  4574.9    0.07       0  4888.7     0.1       0  4989.5    0.05       0
  4993.5     0.1       0
Bank Sta=4989.5,4993.5
Exp/Cntr=0.3,0.1

Type RM Length L Ch R = 1,533,425,425,425
BEGIN DESCRIPTION:
Stream0098 1.0
END DESCRIPTION:
XS GIS Cut Line= 3
      1772275.03     13901024.99      1772625.00     13900875.00
      1772725.01     13900574.98
#Sta/Elev= 30
  4618.0 2240.73  4650.6 2239.57  4679.6 2237.90  4703.2 2237.61  4726.8 2235.95
  4802.9 2232.90  4824.7 2231.05  4868.2 2229.47  4879.1 2229.41  4908.1 2227.48
  4921.3 2227.32  4955.2 2226.33  4977.0 2224.65  5007.2 2223.21  5007.5 2222.71
  5011.1 2222.71  5011.3 2223.21  5019.8 2224.60  5040.9 2226.49  5051.5 2228.20
  5072.5 2229.41  5083.1 2230.70  5104.2 2231.43  5114.7 2232.45  5135.8 2233.44
  5177.9 2236.63  5237.9 2239.31  5283.4 2242.09  5304.4 2244.17  5315.0 2244.65
#Mann=5,-1,0
  4618.0    0.07       0  4921.3     0.1       0  5007.2    0.05       0
  5011.3     0.1       0  5237.9    0.07       0
Bank Sta=5007.2,5011.3
Exp/Cntr=0.3,0.1

Type RM Length L Ch R = 1,108,0,0,0
BEGIN DESCRIPTION:
Stream0098 0.0
END DESCRIPTION:
XS GIS Cut Line= 4
      1772152.12     13901469.29      1772570.91     13901382.50
      1772894.26     13901093.87      1773041.84     13900553.48
#Sta/Elev= 30
  4421.0 2243.45  4518.5 2241.94  4563.6 2239.88  4628.2 2238.21  4848.2 2228.57
  4870.9 2228.55  4912.6 2226.20  4927.7 2225.93  4941.9 2224.00  4948.6 2224.49
  4984.6 2220.92  4991.3 2221.01  4998.8 2219.77  5010.9 2219.44  5011.2 2218.94
  5014.8 2218.94  5015.0 2219.44  5033.9 2221.04  5041.4 2222.63  5062.3 2225.11
  5119.1 2227.56  5152.0 2228.08  5182.7 2227.87  5217.8 2229.10  5305.4 2229.65
  5488.3 2234.79  5633.4 2237.94  5681.8 2240.26  5737.1 2241.17  5842.3 2245.76
#Mann=5,-1,0
  4421.0    0.07       0  4912.6     0.1       0  5010.9    0.05       0
  5015.0     0.1       0  5152.0    0.07       0
Bank Sta=5010.9,5015
Exp/Cntr=0.3,0.1

Chan Stop Cuts=-1