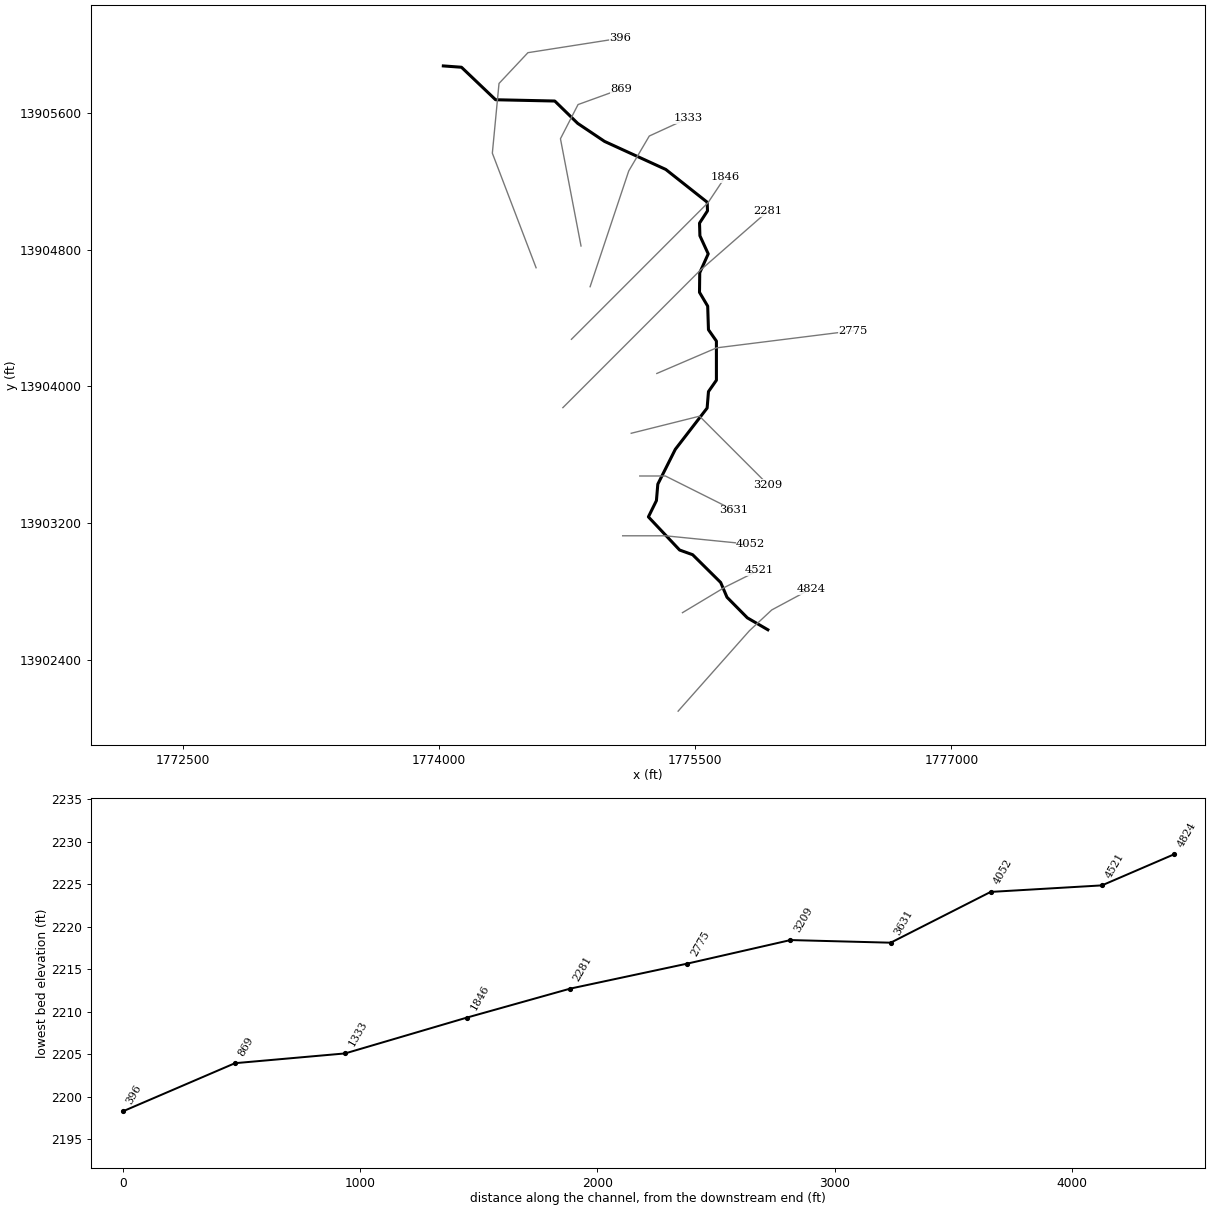
--- Stream0099.prj (project) ---

Proj Title=Stream0099 Base Level Engineering
Current Plan=p01
Default Exp/Contr=0.3,0.1
English Units
Geom File=g01
Flow File=f01
Plan File=p01
BEGIN DESCRIPTION:
Stream0099
END DESCRIPTION:

--- Stream0099.p01 (plan) ---

Plan Title=Multiple Run
Short Identifier=Multiple
Geom File=g01
Flow File=f01
Subcritical Flow
K Sum by GR= 0
Std Step Tol= 0.01
Critical Tol= 0.01
Num of Std Step Trials= 20
Max Error Tol= 0.3
Flow Tol Ratio= 0.001
Split Flow NTrial= 30
Split Flow Tol= 0.02
Split Flow Ratio= 0.02
Log Output Level= 0
Friction Slope Method= 1
Unsteady Friction Slope Method= 2
Unsteady Bridges Friction Slope Method= 1
Parabolic Critical Depth
Global Vel Dist=  1 , 1 , 1
Global Log Level= 0
CheckData=True
Encroach Param= -1, 0, 0, 0
BEGIN DESCRIPTION:
Multiple Run
END DESCRIPTION:

--- Stream0099.f01 (steady flow) ---

Flow Title=Multiple
Number of Profiles=7
Profile Names=10-year,25-year,50-year,1pct_min,100-year,1pct_plu,500-year
River Rch & RM= Stream0099,Reach-1,4824
    1315    2254    3149    2122    4233    8447    7571
Boundary for River Rch & Prof#=Stream0099,Reach-1,1
Up Type=0
Dn Type=3
Dn Slope=0.005
Boundary for River Rch & Prof#=Stream0099,Reach-1,2
Up Type=0
Dn Type=3
Dn Slope=0.005
Boundary for River Rch & Prof#=Stream0099,Reach-1,3
Up Type=0
Dn Type=3
Dn Slope=0.005
Boundary for River Rch & Prof#=Stream0099,Reach-1,4
Up Type=0
Dn Type=3
Dn Slope=0.005
Boundary for River Rch & Prof#=Stream0099,Reach-1,5
Up Type=0
Dn Type=3
Dn Slope=0.005
Boundary for River Rch & Prof#=Stream0099,Reach-1,6
Up Type=0
Dn Type=3
Dn Slope=0.005
Boundary for River Rch & Prof#=Stream0099,Reach-1,7
Up Type=0
Dn Type=3
Dn Slope=0.005

--- Stream0099.g01 (geometry) ---

Geom Title=Existing Conditions

River Reach=Stream0099,Reach-1
Reach XY= 30
      1775925.00     13902575.00      1775804.90     13902644.76
      1775685.78     13902765.32      1775648.70     13902851.82
      1775484.68     13903014.22      1775408.33     13903041.65
      1775225.60     13903235.62      1775272.62     13903330.97
      1775280.77     13903427.32      1775383.16     13903631.05
      1775569.46     13903872.58      1775577.36     13903969.02
      1775623.78     13904035.50      1775623.78     13904264.50
      1775577.27     13904330.94      1775572.73     13904469.06
      1775524.77     13904549.93      1775526.21     13904664.49
      1775575.82     13904775.00      1775527.17     13904880.97
      1775524.92     13904954.91      1775571.66     13905026.75
      1775569.92     13905077.31      1775327.29     13905269.15
      1774968.95     13905433.16      1774811.79     13905538.63
      1774677.45     13905669.54      1774330.85     13905677.06
      1774131.22     13905867.26      1774025.00     13905875.00

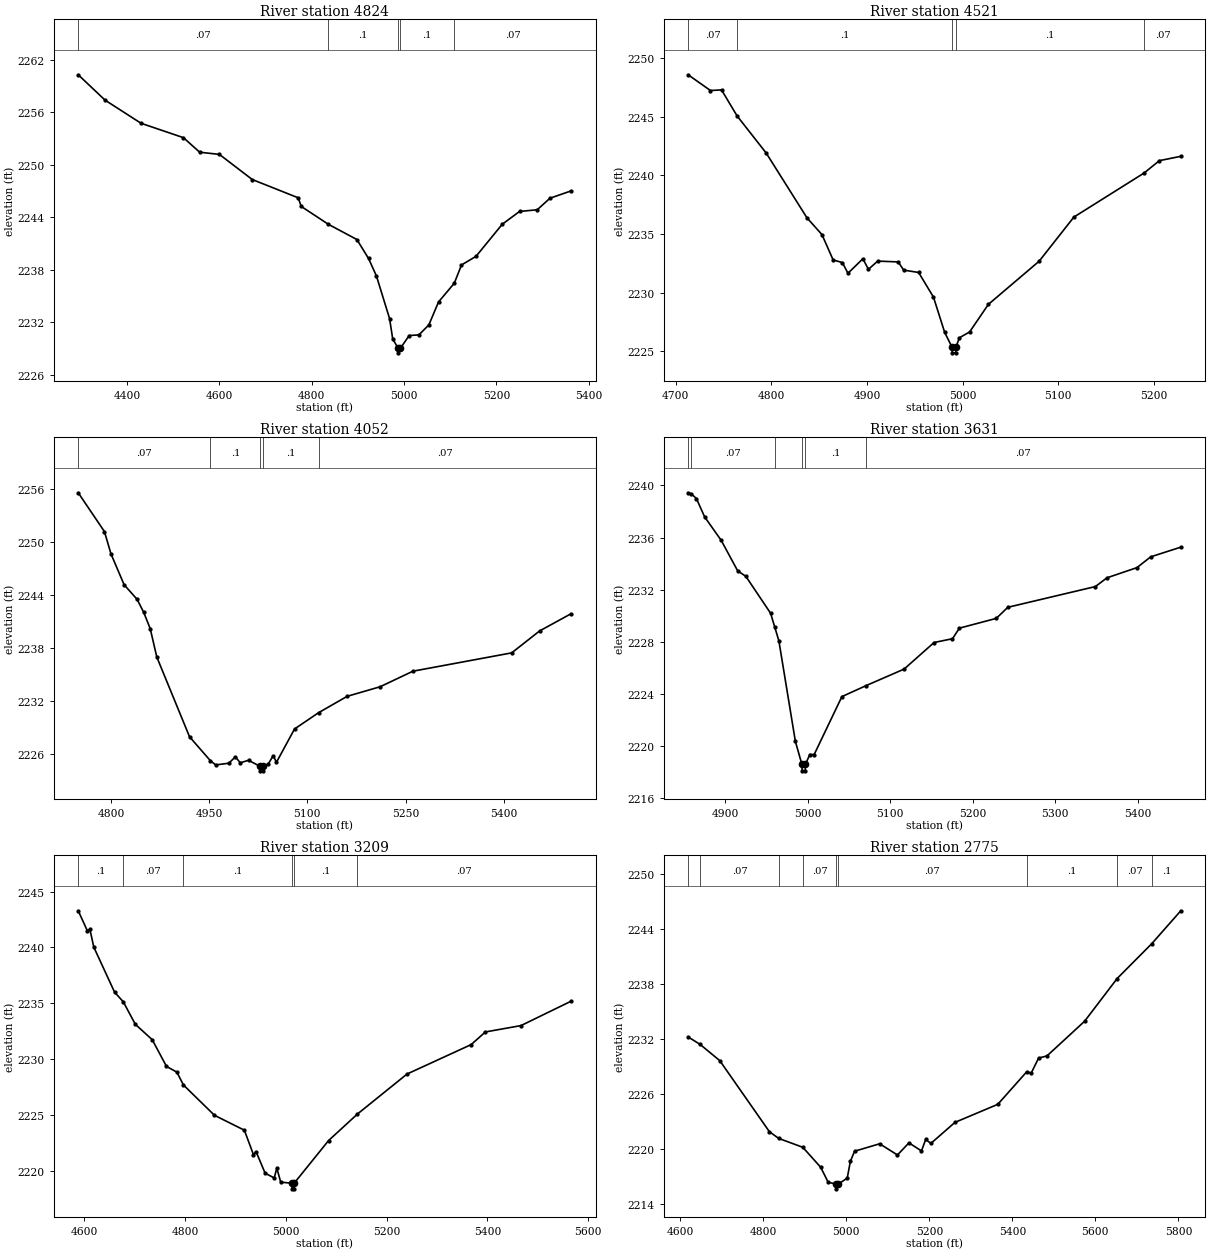
Type RM Length L Ch R = 1,4824,303,303,303
BEGIN DESCRIPTION:
Stream0099 8.0
END DESCRIPTION:
XS GIS Cut Line= 4
      1775399.62     13902098.58      1775816.69     13902568.94
      1775947.80     13902691.00      1776175.99     13902813.58
#Sta/Elev= 30
  4294.6 2260.30  4352.7 2257.40  4430.5 2254.76  4522.5 2253.11  4557.6 2251.45
  4600.3 2251.20  4671.4 2248.33  4770.9 2246.24  4777.6 2245.25  4836.0 2243.22
  4898.0 2241.47  4923.2 2239.31  4940.4 2237.30  4968.8 2232.43  4975.6 2230.11
  4987.7 2229.02  4987.9 2228.52  4991.9 2229.02  5011.3 2230.50  5032.3 2230.57
  5053.8 2231.71  5074.8 2234.33  5109.1 2236.49  5124.5 2238.56  5156.0 2239.55
  5212.7 2243.21  5250.3 2244.68  5288.5 2244.87  5316.1 2246.19  5361.4 2247.02
#Mann=5,-1,0
  4294.6    0.07       0  4836.0     0.1       0  4987.7    0.05       0
  4991.9     0.1       0  5109.1    0.07       0
Bank Sta=4987.7,4991.9
Exp/Cntr=0.3,0.1

Type RM Length L Ch R = 1,4521,469,469,469
BEGIN DESCRIPTION:
Stream0099 7.0
END DESCRIPTION:
XS GIS Cut Line= 3
      1775425.04     13902675.02      1775675.00     13902825.00
      1775874.99     13902925.00
#Sta/Elev= 30
  4712.9 2248.57  4736.2 2247.23  4747.8 2247.28  4764.1 2245.06  4794.5 2241.90
  4837.2 2236.37  4852.8 2234.95  4864.5 2232.79  4874.2 2232.56  4880.0 2231.65
  4895.6 2232.89  4901.4 2231.99  4911.1 2232.69  4932.5 2232.62  4938.3 2231.92
  4953.9 2231.72  4969.4 2229.62  4981.1 2226.62  4988.7 2225.37  4988.9 2224.87
  4992.6 2224.87  4992.9 2225.37  4996.6 2226.16  5007.2 2226.65  5026.8 2229.00
  5079.9 2232.68  5116.2 2236.44  5189.7 2240.20  5205.6 2241.25  5228.0 2241.62
#Mann=5,-1,0
  4712.9    0.07       0  4764.1     0.1       0  4988.7    0.05       0
  4992.9     0.1       0  5189.7    0.07       0
Bank Sta=4988.7,4992.9
Exp/Cntr=0.3,0.1

Type RM Length L Ch R = 1,4052,421,421,421
BEGIN DESCRIPTION:
Stream0099 6.0
END DESCRIPTION:
XS GIS Cut Line= 3
      1775074.96     13903125.00      1775325.00     13903125.00
      1775824.96     13903075.00
#Sta/Elev= 30
  4750.0 2255.52  4790.0 2251.14  4800.0 2248.62  4820.0 2245.14  4840.0 2243.47
  4850.0 2242.01  4860.0 2240.16  4870.0 2236.96  4920.0 2227.95  4951.9 2225.24
  4960.0 2224.77  4980.0 2224.96  4990.0 2225.68  4997.5 2225.01  5010.1 2225.29
  5028.0 2224.60  5028.3 2224.10  5032.0 2224.10  5032.3 2224.60  5040.2 2224.87
  5047.8 2225.81  5052.8 2225.07  5080.4 2228.83  5117.1 2230.67  5160.8 2232.52
  5211.1 2233.60  5261.3 2235.36  5412.1 2237.43  5454.8 2239.91  5502.5 2241.84
#Mann=5,-1,0
  4750.0    0.07       0  4951.9     0.1       0  5028.0    0.05       0
  5032.3     0.1       0  5117.1    0.07       0
Bank Sta=5028,5032.3
Exp/Cntr=0.3,0.1

Type RM Length L Ch R = 1,3631,422,422,422
BEGIN DESCRIPTION:
Stream0099 5.0
END DESCRIPTION:
XS GIS Cut Line= 3
      1775174.96     13903475.00      1775325.00     13903475.00
      1775725.04     13903274.98
#Sta/Elev= 30
  4855.0 2239.44  4858.8 2239.36  4865.0 2239.00  4875.0 2237.59  4895.0 2235.80
  4915.0 2233.46  4925.0 2233.03  4955.0 2230.20  4960.1 2229.12  4965.0 2228.09
  4985.0 2220.38  4992.9 2218.62  4993.2 2218.12  4996.9 2218.12  4997.2 2218.62
  5002.5 2219.37  5007.8 2219.37  5041.4 2223.81  5070.6 2224.65  5116.8 2225.92
  5153.2 2227.96  5175.5 2228.25  5183.9 2229.06  5228.6 2229.81  5242.6 2230.66
  5348.8 2232.25  5362.8 2232.92  5399.1 2233.70  5415.9 2234.53  5452.3 2235.27
#Mann=6,-1,0
  4855.0     0.1       0  4858.8    0.07       0  4960.1     0.1       0
  4992.9    0.05       0  4997.2     0.1       0  5070.6    0.07       0
Bank Sta=4992.9,4997.2
Exp/Cntr=0.3,0.1

Type RM Length L Ch R = 1,3209,434,434,434
BEGIN DESCRIPTION:
Stream0099 4.0
END DESCRIPTION:
XS GIS Cut Line= 3
      1775125.03     13903725.01      1775525.00     13903825.00
      1775925.03     13903424.97
#Sta/Elev= 30
  4587.7 2243.28  4605.7 2241.50  4610.9 2241.61  4618.6 2240.03  4659.8 2236.01
  4677.2 2235.14  4701.1 2233.13  4734.6 2231.76  4762.9 2229.37  4783.5 2228.86
  4796.6 2227.71  4858.2 2225.00  4917.5 2223.67  4935.6 2221.48  4940.7 2221.76
  4958.7 2219.83  4976.8 2219.40  4981.9 2220.28  4989.7 2219.03  5011.9 2218.93
  5012.2 2218.43  5016.0 2218.43  5016.3 2218.93  5084.8 2222.75  5142.1 2225.12
  5240.4 2228.69  5367.7 2231.32  5396.0 2232.45  5466.7 2233.02  5565.7 2235.19
#Mann=6,-1,0
  4587.7     0.1       0  4677.2    0.07       0  4796.6     0.1       0
  5011.9    0.05       0  5016.3     0.1       0  5142.1    0.07       0
Bank Sta=5011.9,5016.3
Exp/Cntr=0.3,0.1

Type RM Length L Ch R = 1,2775,494,494,494
BEGIN DESCRIPTION:
Stream0099 3.0
END DESCRIPTION:
XS GIS Cut Line= 3
      1775274.98     13904074.99      1775625.00     13904225.00
      1776424.96     13904325.00
#Sta/Elev= 30
  4618.8 2232.21  4647.6 2231.40  4695.0 2229.63  4814.7 2221.88  4837.2 2221.15
  4895.0 2220.19  4938.0 2218.02  4956.1 2216.39  4975.7 2216.16  4976.0 2215.66
  4980.1 2216.16  5002.1 2216.83  5009.7 2218.66  5019.8 2219.76  5080.2 2220.57
  5123.1 2219.35  5150.8 2220.67  5181.0 2219.79  5191.1 2221.04  5203.7 2220.61
  5261.6 2222.90  5364.9 2224.87  5434.1 2228.39  5445.6 2228.29  5463.2 2229.91
  5483.3 2230.14  5574.0 2233.92  5652.5 2238.58  5736.2 2242.39  5805.8 2245.96
#Mann=9,-1,0
  4618.8     0.1       0  4647.6    0.07       0  4837.2   0.035       0
  4895.0    0.07       0  4975.7    0.05       0  4980.1    0.07       0
  5434.1     0.1       0  5652.5    0.07       0  5736.2     0.1       0
Bank Sta=4975.7,4980.1
Exp/Cntr=0.3,0.1

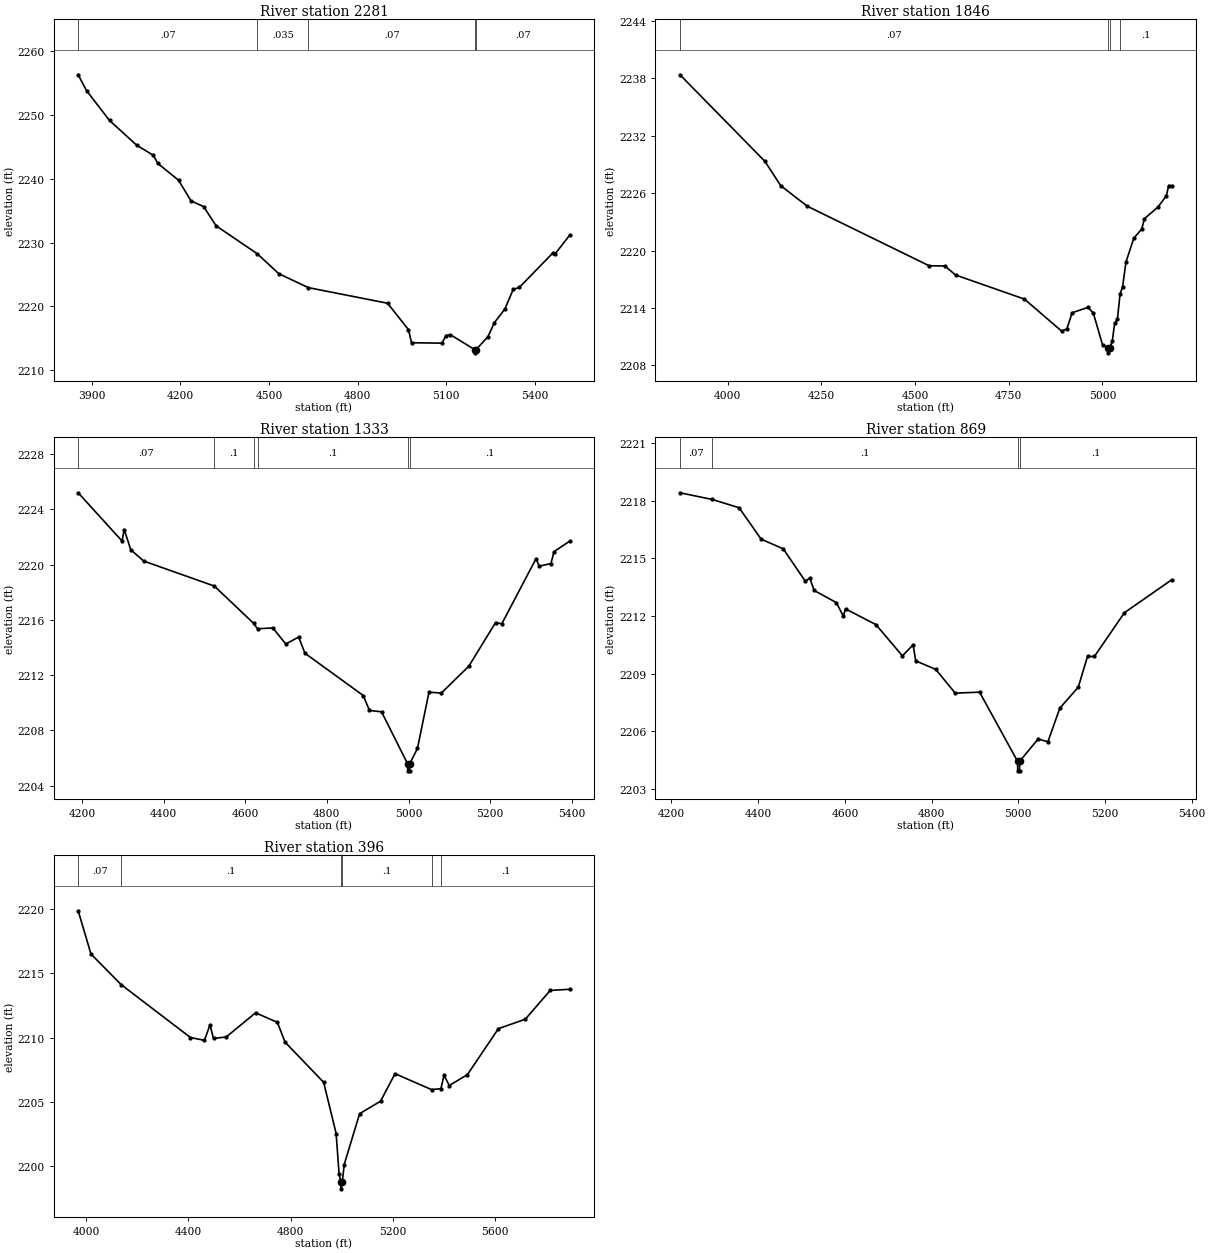
Type RM Length L Ch R = 1,2281,435,435,435
BEGIN DESCRIPTION:
Stream0099 2.0
END DESCRIPTION:
XS GIS Cut Line= 3
      1774724.97     13903874.97      1775525.00     13904675.00
      1775924.98     13905024.98
#Sta/Elev= 30
  3854.6 2256.33  3882.9 2253.84  3960.7 2249.16  4052.6 2245.28  4109.2 2243.69
  4123.3 2242.45  4194.1 2239.79  4236.5 2236.54  4278.9 2235.65  4321.3 2232.64
  4460.5 2228.25  4533.5 2225.12  4633.4 2222.94  4901.2 2220.49  4971.9 2216.36
  4982.5 2214.29  5085.2 2214.23  5099.4 2215.43  5113.7 2215.56  5196.4 2213.21
  5196.7 2212.71  5200.8 2213.21  5240.9 2215.25  5262.7 2217.45  5297.8 2219.56
  5326.3 2222.65  5347.2 2222.98  5461.1 2228.41  5467.7 2228.21  5517.5 2231.17
#Mann=5,-1,0
  3854.6    0.07       0  4460.5   0.035       0  4633.4    0.07       0
  5196.4    0.05       0  5200.8    0.07       0
Bank Sta=5196.4,5200.8
Exp/Cntr=0.3,0.1

Type RM Length L Ch R = 1,1846,513,513,513
BEGIN DESCRIPTION:
Stream0099 1.0
END DESCRIPTION:
XS GIS Cut Line= 3
      1774775.00     13904275.00      1775575.00     13905075.00
      1775675.03     13905225.04
#Sta/Elev= 30
  3872.5 2238.38  4098.8 2229.34  4141.2 2226.79  4211.9 2224.64  4537.2 2218.41
  4579.6 2218.38  4607.9 2217.44  4791.7 2214.92  4890.7 2211.58  4904.9 2211.80
  4919.0 2213.49  4961.4 2214.06  4975.6 2213.45  5000.3 2210.11  5014.9 2209.80
  5015.3 2209.30  5019.8 2209.80  5026.4 2210.59  5032.4 2212.39  5039.9 2212.83
  5046.9 2215.48  5053.5 2216.17  5062.5 2218.78  5083.5 2221.29  5104.5 2222.24
  5112.0 2223.33  5148.1 2224.55  5170.6 2225.74  5176.6 2226.80  5184.2 2226.78
#Mann=4,-1,0
  3872.5    0.07       0  5014.9    0.05       0  5019.8    0.07       0
  5046.9     0.1       0
Bank Sta=5014.9,5019.8
Exp/Cntr=0.3,0.1

Type RM Length L Ch R = 1,1333,464,464,464
BEGIN DESCRIPTION:
Stream0099 0.0
END DESCRIPTION:
XS GIS Cut Line= 4
      1774884.39     13904582.88      1775110.51     13905260.31
      1775230.78     13905464.67      1775459.97     13905569.94
#Sta/Elev= 30
  4191.1 2225.20  4298.5 2221.71  4303.8 2222.54  4319.8 2221.08  4351.5 2220.26
  4524.5 2218.45  4620.4 2215.76  4630.2 2215.36  4667.7 2215.42  4699.4 2214.26
  4731.0 2214.76  4746.3 2213.59  4889.1 2210.53  4904.3 2209.45  4933.9 2209.35
  4997.8 2205.58  4998.2 2205.08  5002.4 2205.08  5002.7 2205.58  5021.8 2206.70
  5050.0 2210.77  5080.3 2210.71  5147.5 2212.65  5213.1 2215.81  5228.3 2215.72
  5312.1 2220.43  5320.2 2219.89  5348.7 2220.08  5356.1 2220.94  5394.6 2221.70
#Mann=6,-1,0
  4191.1    0.07       0  4524.5     0.1       0  4620.4    0.07       0
  4630.2     0.1       0  4997.8    0.05       0  5002.7     0.1       0
Bank Sta=4997.8,5002.7
Exp/Cntr=0.3,0.1

Type RM Length L Ch R = 1,869,473,473,473
BEGIN DESCRIPTION:
Stream0099 0.1
END DESCRIPTION:
XS GIS Cut Line= 4
      1774831.12     13904821.05      1774710.73     13905448.89
      1774813.69     13905648.82      1775067.23     13905740.60
#Sta/Elev= 30
  4219.6 2218.42  4294.3 2218.07  4356.0 2217.64  4406.9 2216.00  4457.8 2215.50
  4508.7 2213.81  4518.9 2213.98  4529.1 2213.33  4580.0 2212.70  4596.3 2212.00
  4601.4 2212.37  4671.6 2211.55  4732.7 2209.92  4757.4 2210.50  4763.3 2209.66
  4809.4 2209.22  4854.4 2207.98  4910.7 2208.03  4998.2 2204.43  4998.6 2203.93
  5002.8 2203.93  5003.2 2204.43  5045.7 2205.59  5068.2 2205.44  5095.8 2207.20
  5138.3 2208.29  5159.6 2209.89  5175.5 2209.89  5244.7 2212.17  5353.4 2213.88
#Mann=4,-1,0
  4219.6    0.07       0  4294.3     0.1       0  4998.2    0.05       0
  5003.2     0.1       0
Bank Sta=4998.2,5003.2
Exp/Cntr=0.3,0.1

Type RM Length L Ch R = 1,396,0,0,0
BEGIN DESCRIPTION:
Stream0099 0.2
END DESCRIPTION:
XS GIS Cut Line= 5
      1774568.03     13904693.80      1774311.95     13905364.38
      1774351.01     13905772.37      1774520.28     13905952.49
      1775060.35     13906037.08
#Sta/Elev= 30
  3969.9 2219.86  4019.9 2216.50  4138.0 2214.12  4408.8 2210.01  4463.6 2209.79
  4485.0 2210.99  4499.0 2209.94  4548.4 2210.05  4663.4 2211.93  4748.6 2211.19
  4778.7 2209.65  4929.4 2206.53  4978.3 2202.55  4989.7 2199.42  4997.3 2198.75
  4997.7 2198.25  5002.3 2198.75  5009.8 2200.14  5070.1 2204.09  5151.9 2205.06
  5208.5 2207.20  5351.4 2205.96  5387.9 2206.04  5400.1 2207.08  5420.4 2206.28
  5491.2 2207.12  5612.7 2210.70  5717.7 2211.43  5815.1 2213.67  5891.4 2213.76
#Mann=6,-1,0
  3969.9    0.07       0  4138.0     0.1       0  4997.3    0.05       0
  5002.3     0.1       0  5351.4    0.07       0  5387.9     0.1       0
Bank Sta=4997.3,5002.3
Exp/Cntr=0.3,0.1

Chan Stop Cuts=-1