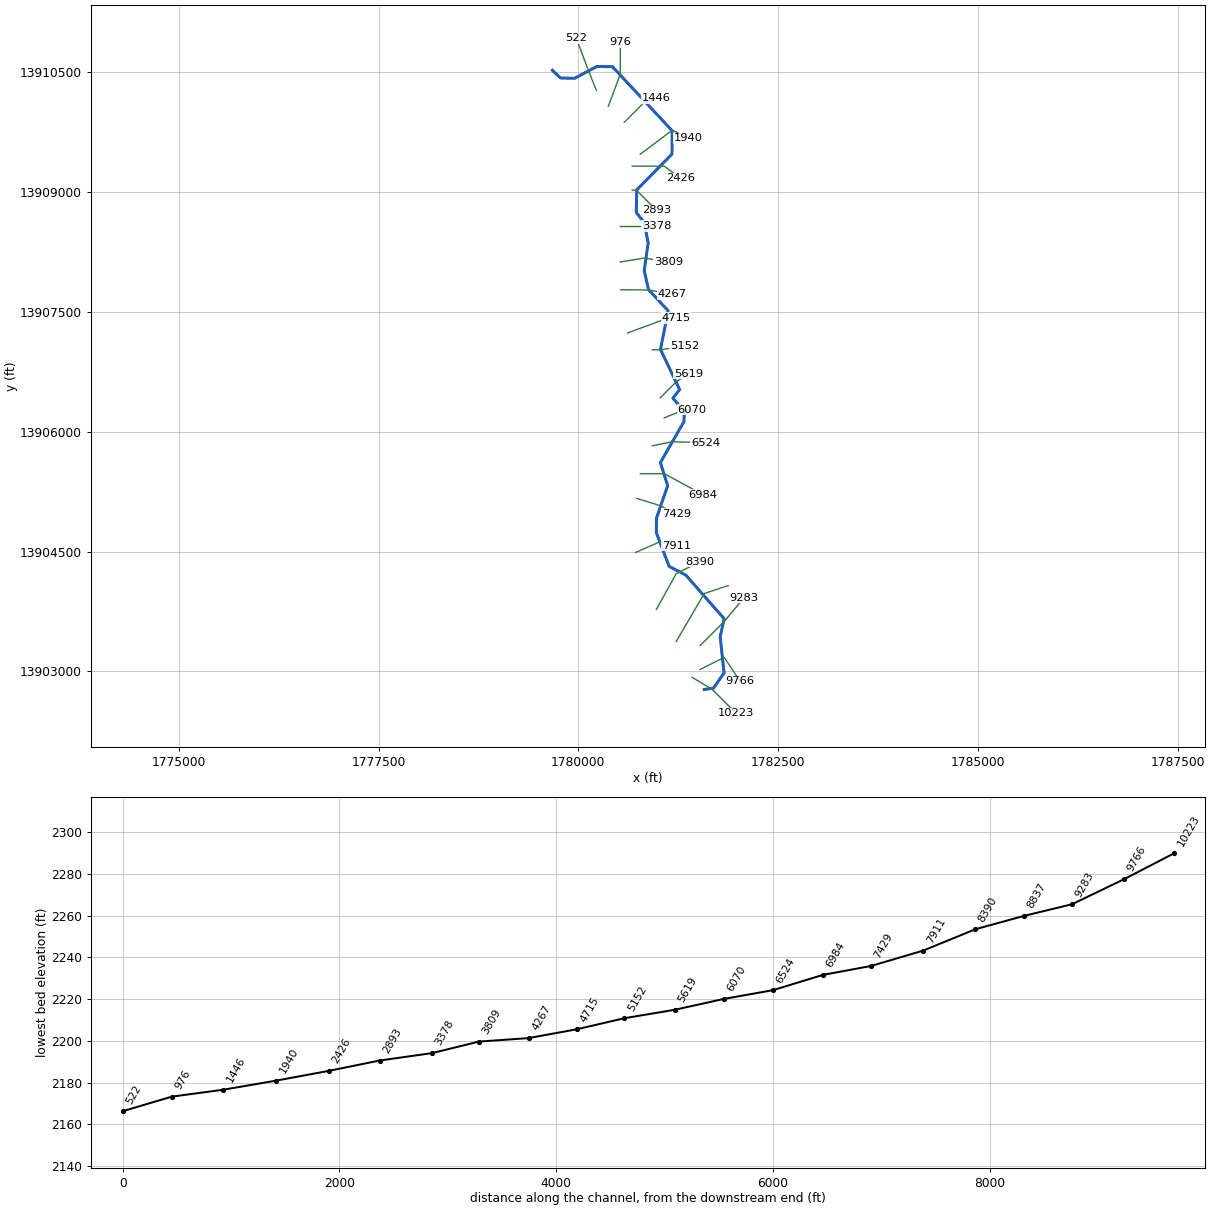
--- Stream0100.prj (project) ---

Proj Title=Stream0100 Base Level Engineering
Current Plan=p01
Default Exp/Contr=0.3,0.1
English Units
Geom File=g01
Flow File=f01
Plan File=p01
BEGIN DESCRIPTION:
Stream0100
END DESCRIPTION:

--- Stream0100.p01 (plan) ---

Plan Title=Multiple Run
Short Identifier=Multiple
Geom File=g01
Flow File=f01
Subcritical Flow
K Sum by GR= 0
Std Step Tol= 0.01
Critical Tol= 0.01
Num of Std Step Trials= 20
Max Error Tol= 0.3
Flow Tol Ratio= 0.001
Split Flow NTrial= 30
Split Flow Tol= 0.02
Split Flow Ratio= 0.02
Log Output Level= 0
Friction Slope Method= 1
Unsteady Friction Slope Method= 2
Unsteady Bridges Friction Slope Method= 1
Parabolic Critical Depth
Global Vel Dist=  1 , 1 , 1
Global Log Level= 0
CheckData=True
Encroach Param= -1, 0, 0, 0
BEGIN DESCRIPTION:
Multiple Run
END DESCRIPTION:

--- Stream0100.f01 (steady flow) ---

Flow Title=Multiple
Number of Profiles=7
Profile Names=10-year,25-year,50-year,1pct_min,100-year,1pct_plu,500-year
River Rch & RM= Stream0100,Reach-1,10223
     405     651     871     566    1130    2255    1873
River Rch & RM= Stream0100,Reach-1,8390
    1107    1891    2636    1775    3542    7067    6323
River Rch & RM= Stream0100,Reach-1,2426
    1354    2348    3306    2247    4483    8944    8156
Boundary for River Rch & Prof#=Stream0100,Reach-1,1
Up Type=0
Dn Type=3
Dn Slope=0.005
Boundary for River Rch & Prof#=Stream0100,Reach-1,2
Up Type=0
Dn Type=3
Dn Slope=0.005
Boundary for River Rch & Prof#=Stream0100,Reach-1,3
Up Type=0
Dn Type=3
Dn Slope=0.005
Boundary for River Rch & Prof#=Stream0100,Reach-1,4
Up Type=0
Dn Type=3
Dn Slope=0.005
Boundary for River Rch & Prof#=Stream0100,Reach-1,5
Up Type=0
Dn Type=3
Dn Slope=0.005
Boundary for River Rch & Prof#=Stream0100,Reach-1,6
Up Type=0
Dn Type=3
Dn Slope=0.005
Boundary for River Rch & Prof#=Stream0100,Reach-1,7
Up Type=0
Dn Type=3
Dn Slope=0.005

--- Stream0100.g01 (geometry) ---

Geom Title=Existing Conditions

River Reach=Stream0100,Reach-1
Reach XY= 30
      1781575.00     13902775.00      1781688.72     13902788.19
      1781822.94     13902980.86      1781774.50     13903435.17
      1781824.51     13903659.78      1781345.15     13904205.37
      1781135.51     13904315.19      1780976.22     13904735.51
      1780977.26     13904919.06      1781117.44     13905325.00
      1781026.09     13905614.46      1781321.26     13906126.56
      1781325.06     13906255.01      1781182.61     13906421.67
      1781267.15     13906528.23      1781027.26     13907030.94
      1781123.95     13907514.57      1780877.06     13907780.85
      1780824.12     13908019.62      1780873.79     13908364.49
      1780821.45     13908623.53      1780724.96     13908744.98
      1780730.46     13909027.45      1781171.45     13909476.47
      1781172.94     13909769.15      1780427.45     13910569.54
      1780230.93     13910572.76      1779954.97     13910425.06
      1779776.44     13910428.48      1779675.00     13910525.00

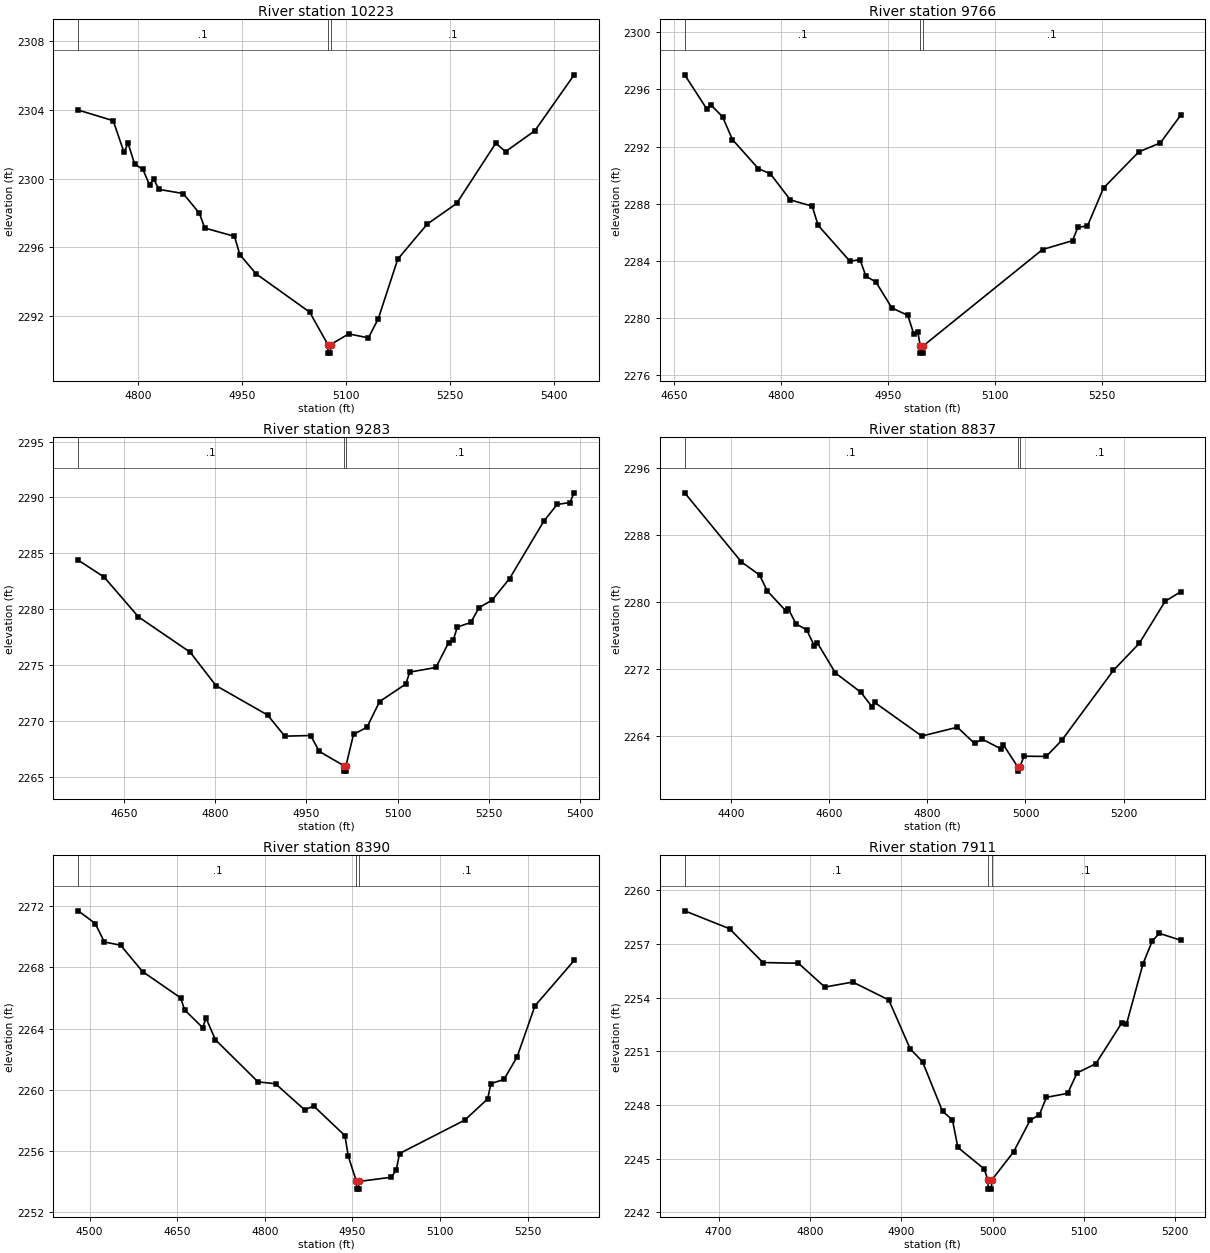
Type RM Length L Ch R = 1,10223,457,457,457
BEGIN DESCRIPTION:
Stream0100 22.0
END DESCRIPTION:
XS GIS Cut Line= 3
      1781425.00     13902925.00      1781675.00     13902775.00
      1781975.00     13902475.00
#Sta/Elev= 30
  4713.0 2304.00  4763.5 2303.38  4779.1 2301.54  4784.9 2302.07  4794.6 2300.84
  4806.3 2300.55  4816.0 2299.64  4821.8 2299.98  4829.6 2299.38  4864.6 2299.14
  4887.9 2297.99  4895.7 2297.13  4938.5 2296.65  4946.2 2295.59  4969.6 2294.47
  5047.0 2292.24  5073.3 2290.35  5073.5 2289.85  5077.0 2289.85  5077.3 2290.35
  5103.5 2290.97  5131.8 2290.74  5146.0 2291.84  5174.2 2295.32  5216.7 2297.36
  5259.1 2298.56  5315.7 2302.07  5329.8 2301.58  5372.2 2302.80  5428.8 2306.05
#Mann=3,-1,0
  4713.0     0.1       0  5073.3    0.05       0  5077.3     0.1       0
Bank Sta=5073.3,5077.3
Exp/Cntr=0.3,0.1

Type RM Length L Ch R = 1,9766,483,483,483
BEGIN DESCRIPTION:
Stream0100 21.0
END DESCRIPTION:
XS GIS Cut Line= 3
      1781524.97     13903024.99      1781825.00     13903175.00
      1782025.00     13902875.00
#Sta/Elev= 30
  4664.4 2297.01  4695.2 2294.64  4700.8 2294.93  4717.5 2294.08  4731.5 2292.48
  4767.9 2290.45  4784.6 2290.10  4812.6 2288.27  4843.3 2287.83  4851.7 2286.49
  4896.4 2283.98  4910.4 2284.10  4918.8 2282.93  4932.8 2282.53  4955.1 2280.72
  4977.5 2280.20  4985.9 2278.91  4991.5 2279.06  4995.0 2278.06  4995.3 2277.56
  4998.8 2277.56  4999.0 2278.06  5166.6 2284.80  5208.7 2285.42  5216.2 2286.35
  5229.7 2286.45  5252.2 2289.10  5301.8 2291.63  5331.9 2292.25  5360.4 2294.18
#Mann=3,-1,0
  4664.4     0.1       0  4995.0    0.05       0  4999.0     0.1       0
Bank Sta=4995,4999
Exp/Cntr=0.3,0.1

Type RM Length L Ch R = 1,9283,446,446,446
BEGIN DESCRIPTION:
Stream0100 20.0
END DESCRIPTION:
XS GIS Cut Line= 3
      1781524.98     13903324.98      1781825.00     13903625.00
      1782074.99     13903924.99
#Sta/Elev= 30
  4575.0 2284.38  4617.5 2282.87  4674.0 2279.30  4758.9 2276.14  4801.3 2273.15
  4886.2 2270.51  4914.4 2268.62  4956.9 2268.68  4971.0 2267.26  5011.0 2265.99
  5011.2 2265.49  5014.7 2265.49  5015.0 2265.99  5027.3 2268.78  5049.4 2269.42
  5070.2 2271.72  5113.2 2273.29  5119.7 2274.36  5162.7 2274.77  5183.5 2276.99
  5191.3 2277.23  5197.8 2278.39  5219.9 2278.80  5233.6 2280.13  5255.1 2280.81
  5283.7 2282.73  5339.7 2287.85  5361.8 2289.37  5382.7 2289.54  5389.8 2290.41
#Mann=3,-1,0
  4575.0     0.1       0  5011.0    0.05       0  5015.0     0.1       0
Bank Sta=5011,5015
Exp/Cntr=0.3,0.1

Type RM Length L Ch R = 1,8837,447,447,447
BEGIN DESCRIPTION:
Stream0100 19.0
END DESCRIPTION:
XS GIS Cut Line= 3
      1781225.01     13903375.02      1781575.00     13903975.00
      1781874.98     13904074.99
#Sta/Elev= 30
  4305.4 2293.04  4421.1 2284.80  4457.9 2283.25  4473.7 2281.35  4510.9 2279.01
  4516.7 2279.20  4532.4 2277.41  4553.9 2276.72  4569.6 2274.81  4575.4 2275.20
  4612.6 2271.57  4664.3 2269.28  4687.0 2267.56  4692.8 2268.05  4788.7 2264.05
  4861.1 2265.10  4896.2 2263.18  4911.9 2263.68  4949.1 2262.55  4954.9 2263.01
  4984.3 2260.37  4984.6 2259.87  4988.3 2260.37  4997.1 2261.65  5042.2 2261.62
  5073.8 2263.53  5179.2 2271.88  5231.9 2275.10  5284.6 2280.11  5316.2 2281.24
#Mann=3,-1,0
  4305.4     0.1       0  4984.3    0.05       0  4988.3     0.1       0
Bank Sta=4984.3,4988.3
Exp/Cntr=0.3,0.1

Type RM Length L Ch R = 1,8390,479,479,479
BEGIN DESCRIPTION:
Stream0100 18.0
END DESCRIPTION:
XS GIS Cut Line= 3
      1780975.16     13903775.82      1781225.00     13904225.00
      1781525.00     13904375.00
#Sta/Elev= 30
  4480.5 2271.71  4509.6 2270.88  4525.3 2269.67  4553.1 2269.46  4590.8 2267.73
  4656.0 2266.01  4662.6 2265.23  4693.7 2264.06  4699.4 2264.69  4715.4 2263.27
  4788.5 2260.51  4818.4 2260.39  4868.6 2258.67  4883.6 2258.94  4937.3 2256.99
  4943.0 2255.65  4957.0 2253.99  4957.3 2253.49  4960.8 2253.49  4961.0 2253.99
  5016.8 2254.27  5025.2 2254.74  5030.8 2255.82  5142.6 2258.01  5181.8 2259.40
  5187.3 2260.40  5209.7 2260.67  5232.1 2262.14  5262.8 2265.49  5329.9 2268.46
#Mann=3,-1,0
  4480.5     0.1       0  4957.0    0.05       0  4961.0     0.1       0
Bank Sta=4957,4961
Exp/Cntr=0.3,0.1

Type RM Length L Ch R = 1,7911,482,482,482
BEGIN DESCRIPTION:
Stream0100 17.0
END DESCRIPTION:
XS GIS Cut Line= 3
      1780716.52     13904489.66      1781025.00     13904625.00
      1781224.98     13904575.00
#Sta/Elev= 30
  4662.8 2258.85  4711.9 2257.85  4748.5 2255.96  4787.4 2255.92  4816.2 2254.59
  4846.8 2254.87  4886.3 2253.87  4909.7 2251.14  4923.2 2250.42  4945.1 2247.65
  4956.0 2247.17  4961.9 2245.63  4990.7 2244.43  4994.9 2243.80  4995.2 2243.30
  4998.7 2243.30  4998.9 2243.80  5022.9 2245.38  5040.9 2247.14  5051.2 2247.46
  5058.9 2248.43  5082.1 2248.65  5092.4 2249.79  5113.0 2250.31  5141.4 2252.59
  5146.5 2252.51  5164.6 2255.89  5174.9 2257.18  5182.6 2257.59  5205.8 2257.21
#Mann=3,-1,0
  4662.8     0.1       0  4994.9    0.05       0  4998.9     0.1       0
Bank Sta=4994.9,4998.9
Exp/Cntr=0.3,0.1

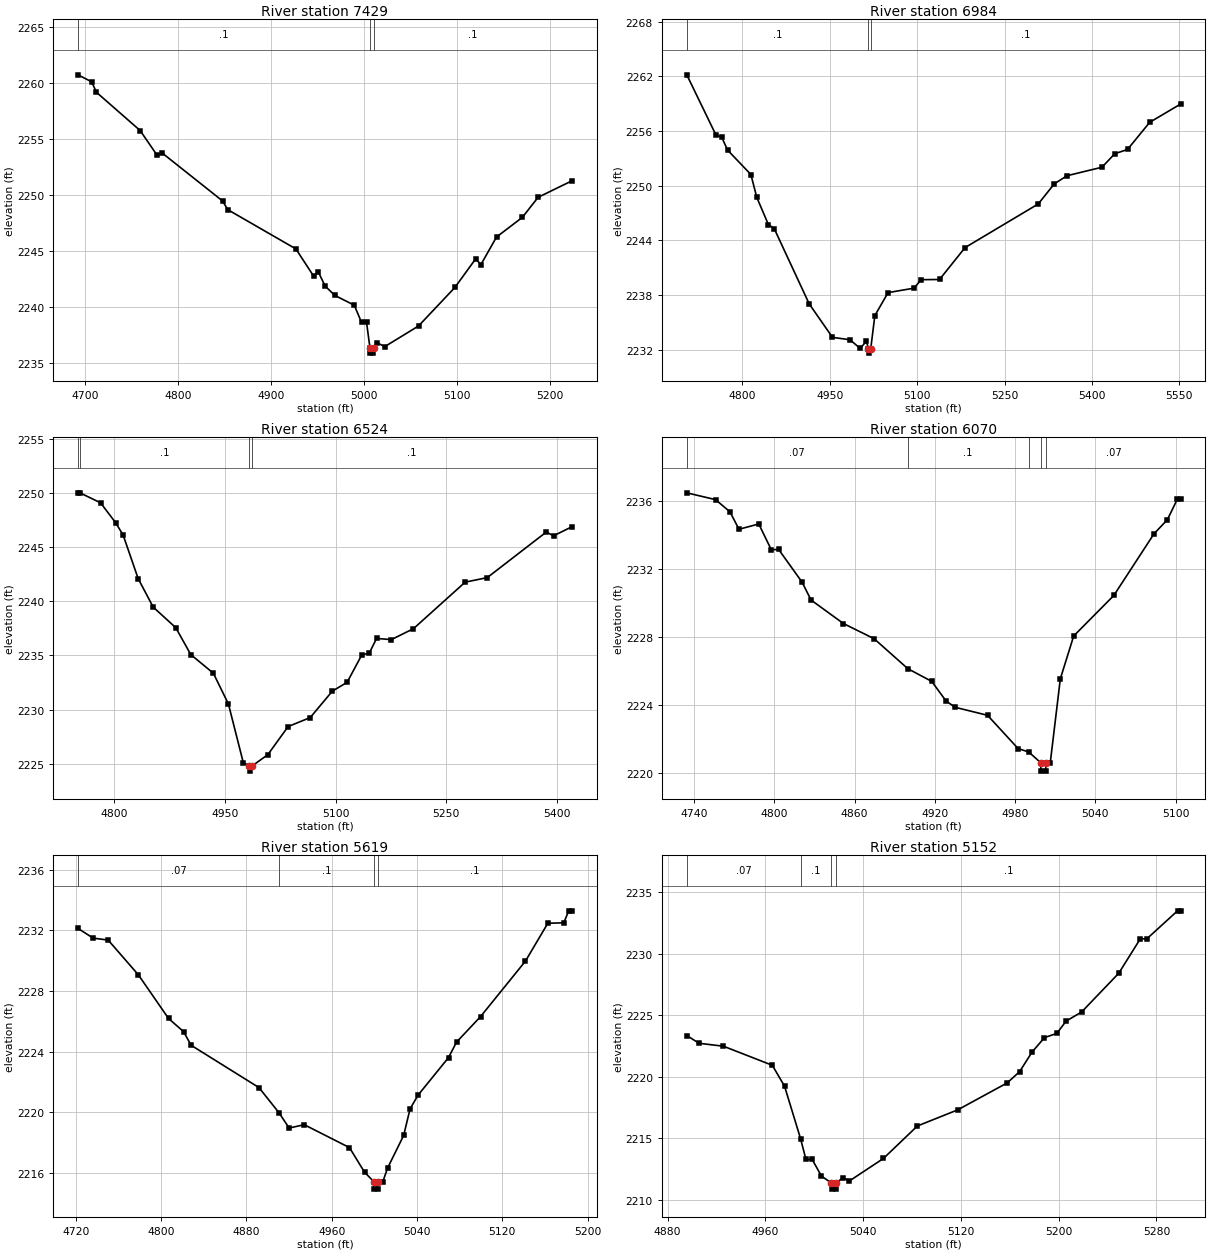
Type RM Length L Ch R = 1,7429,445,445,445
BEGIN DESCRIPTION:
Stream0100 16.0
END DESCRIPTION:
XS GIS Cut Line= 3
      1780731.09     13905165.91      1781025.00     13905075.00
      1781225.04     13904974.98
#Sta/Elev= 30
  4692.7 2260.72  4707.3 2260.10  4712.6 2259.16  4759.6 2255.75  4777.8 2253.55
  4783.1 2253.76  4848.3 2249.47  4853.8 2248.70  4927.1 2245.20  4946.2 2242.77
  4951.4 2243.12  4958.5 2241.89  4968.9 2241.06  4989.9 2240.18  4997.7 2238.65
  5003.1 2238.65  5006.7 2236.41  5007.0 2235.91  5010.5 2235.91  5010.7 2236.41
  5014.3 2236.84  5022.7 2236.49  5059.0 2238.33  5098.2 2241.77  5120.5 2244.32
  5126.1 2243.80  5142.9 2246.26  5170.8 2248.02  5187.6 2249.80  5224.0 2251.27
#Mann=3,-1,0
  4692.7     0.1       0  5006.7    0.05       0  5010.7     0.1       0
Bank Sta=5006.7,5010.7
Exp/Cntr=0.3,0.1

Type RM Length L Ch R = 1,6984,460,460,460
BEGIN DESCRIPTION:
Stream0100 15.0
END DESCRIPTION:
XS GIS Cut Line= 3
      1780775.04     13905475.00      1781075.00     13905475.00
      1781556.86     13905214.76
#Sta/Elev= 30
  4704.7 2262.17  4754.7 2255.57  4764.7 2255.32  4774.7 2253.91  4814.7 2251.23
  4824.7 2248.74  4844.7 2245.74  4854.7 2245.30  4914.7 2237.04  4954.7 2233.36
  4984.7 2233.10  5002.2 2232.15  5012.8 2232.93  5016.4 2232.13  5016.7 2231.63
  5020.4 2232.13  5027.4 2235.75  5050.1 2238.27  5094.6 2238.76  5106.9 2239.69
  5138.4 2239.71  5182.2 2243.21  5307.8 2248.00  5335.4 2250.21  5357.3 2251.10
  5417.2 2252.03  5439.1 2253.51  5461.0 2253.98  5499.1 2256.96  5552.3 2258.97
#Mann=3,-1,0
  4704.7     0.1       0  5016.4    0.05       0  5020.4     0.1       0
Bank Sta=5016.4,5020.4
Exp/Cntr=0.3,0.1

Type RM Length L Ch R = 1,6524,454,454,454
BEGIN DESCRIPTION:
Stream0100 14.0
END DESCRIPTION:
XS GIS Cut Line= 3
      1780924.96     13905824.99      1781175.00     13905875.00
      1781589.79     13905865.12
#Sta/Elev= 30
  4750.7 2249.99  4753.6 2249.98  4781.3 2249.07  4801.7 2247.24  4811.9 2246.10
  4832.3 2242.08  4852.7 2239.45  4883.3 2237.55  4903.7 2235.07  4934.3 2233.35
  4954.7 2230.52  4975.1 2225.05  4983.3 2224.82  4983.5 2224.32  4987.3 2224.82
  5008.2 2225.84  5035.7 2228.43  5065.7 2229.26  5095.7 2231.70  5115.7 2232.51
  5135.7 2235.05  5145.7 2235.20  5155.7 2236.56  5175.7 2236.45  5205.7 2237.46
  5275.8 2241.75  5305.8 2242.17  5385.8 2246.37  5395.8 2246.03  5420.6 2246.86
#Mann=4,-1,0
  4750.7    0.07       0  4753.6     0.1       0  4983.3    0.05       0
  4987.3     0.1       0
Bank Sta=4983.3,4987.3
Exp/Cntr=0.3,0.1

Type RM Length L Ch R = 1,6070,451,451,451
BEGIN DESCRIPTION:
Stream0100 13.0
END DESCRIPTION:
XS GIS Cut Line= 3
      1781075.03     13906175.01      1781325.00     13906275.00
      1781424.97     13906275.00
#Sta/Elev= 30
  4734.6 2236.47  4756.1 2236.07  4766.9 2235.35  4773.6 2234.33  4788.4 2234.64
  4797.8 2233.12  4803.2 2233.15  4820.7 2231.23  4827.5 2230.17  4851.7 2228.79
  4874.6 2227.90  4899.8 2226.14  4917.7 2225.39  4928.4 2224.24  4935.2 2223.87
  4959.4 2223.40  4982.3 2221.44  4990.1 2221.25  4999.1 2220.62  4999.4 2220.12
  5002.9 2220.12  5003.1 2220.62  5006.3 2220.62  5013.8 2225.54  5023.8 2228.06
  5053.8 2230.44  5083.8 2234.06  5093.8 2234.89  5101.3 2236.10  5103.8 2236.10
#Mann=5,-1,0
  4734.6    0.07       0  4899.8     0.1       0  4990.1    0.07       0
  4999.1    0.05       0  5003.1    0.07       0
Bank Sta=4999.1,5003.1
Exp/Cntr=0.3,0.1

Type RM Length L Ch R = 1,5619,467,467,467
BEGIN DESCRIPTION:
Stream0100 12.0
END DESCRIPTION:
XS GIS Cut Line= 3
      1781024.97     13906424.97      1781225.00     13906625.00
      1781375.04     13906725.02
#Sta/Elev= 30
  4722.1 2232.13  4736.3 2231.49  4750.4 2231.36  4778.7 2229.07  4807.0 2226.19
  4821.1 2225.32  4828.2 2224.42  4891.8 2221.63  4910.6 2219.97  4920.1 2218.96
  4934.3 2219.18  4976.7 2217.67  4990.8 2216.05  4999.4 2215.43  4999.7 2214.93
  5003.2 2214.93  5003.4 2215.43  5008.0 2215.43  5012.5 2216.33  5027.5 2218.47
  5033.5 2220.22  5041.0 2221.13  5069.6 2223.61  5077.1 2224.63  5099.6 2226.31
  5141.7 2229.97  5162.7 2232.47  5177.7 2232.50  5182.3 2233.29  5185.3 2233.29
#Mann=4,-1,0
  4722.1    0.07       0  4910.6     0.1       0  4999.4    0.05       0
  5003.4     0.1       0
Bank Sta=4999.4,5003.4
Exp/Cntr=0.3,0.1

Type RM Length L Ch R = 1,5152,437,437,437
BEGIN DESCRIPTION:
Stream0100 11.0
END DESCRIPTION:
XS GIS Cut Line= 3
      1780924.97     13907025.00      1781025.00     13907025.00
      1781325.03     13907075.01
#Sta/Elev= 30
  4895.7 2223.35  4905.7 2222.72  4925.7 2222.48  4965.7 2220.93  4975.7 2219.23
  4988.8 2214.97  4993.2 2213.28  4998.3 2213.28  5005.9 2211.93  5014.0 2211.37
  5014.3 2210.87  5017.8 2210.87  5018.0 2211.37  5023.6 2211.81  5028.7 2211.53
  5056.6 2213.36  5084.4 2216.00  5117.4 2217.31  5157.9 2219.50  5168.1 2220.42
  5178.2 2222.00  5188.4 2223.18  5198.5 2223.52  5206.1 2224.52  5218.8 2225.26
  5249.2 2228.41  5266.9 2231.22  5272.0 2231.19  5297.3 2233.48  5299.9 2233.48
#Mann=4,-1,0
  4895.7    0.07       0  4988.8     0.1       0  5014.0    0.05       0
  5018.0     0.1       0
Bank Sta=5014,5018
Exp/Cntr=0.3,0.1

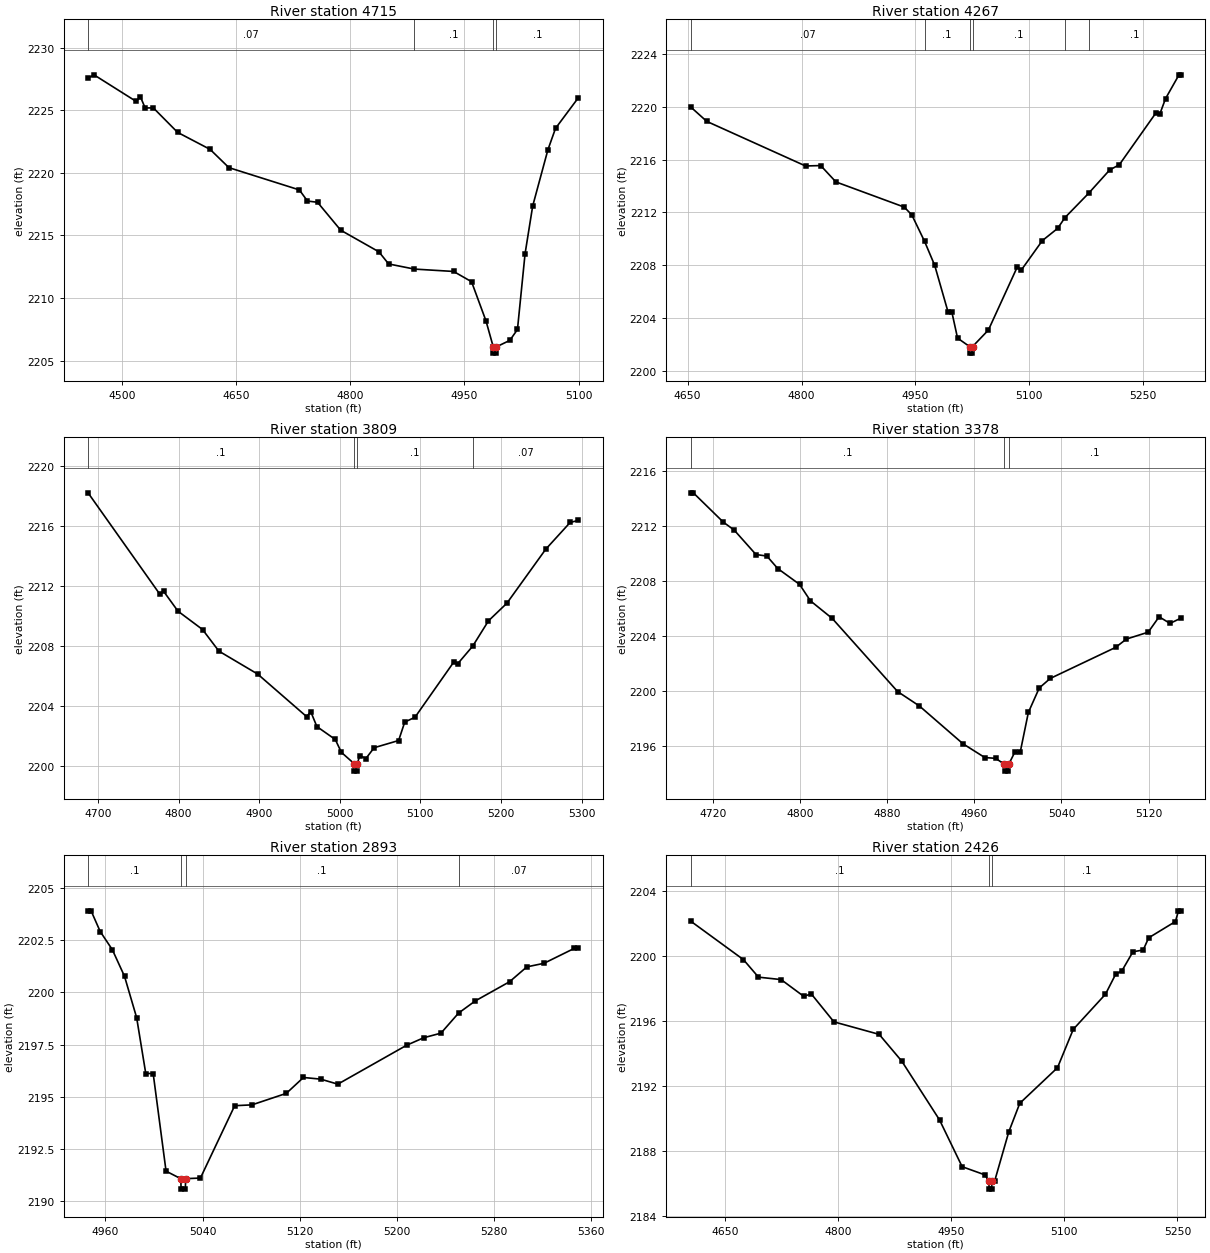
Type RM Length L Ch R = 1,4715,448,448,448
BEGIN DESCRIPTION:
Stream0100 10.0
END DESCRIPTION:
XS GIS Cut Line= 3
      1780614.64     13907236.56      1781125.00     13907425.00
      1781224.96     13907425.00
#Sta/Elev= 30
  4455.8 2227.57  4463.6 2227.84  4519.1 2225.71  4524.5 2226.09  4530.8 2225.19
  4541.5 2225.20  4573.4 2223.24  4616.1 2221.88  4640.8 2220.42  4733.3 2218.64
  4744.0 2217.75  4757.2 2217.65  4787.6 2215.42  4837.8 2213.69  4850.6 2212.72
  4884.3 2212.31  4935.9 2212.12  4959.5 2211.30  4978.5 2208.16  4988.0 2206.09
  4988.2 2205.59  4991.7 2205.59  4992.0 2206.09  5009.8 2206.61  5019.8 2207.48
  5029.8 2213.54  5039.8 2217.35  5059.8 2221.85  5069.8 2223.56  5099.8 2226.01
#Mann=4,-1,0
  4455.8    0.07       0  4884.3     0.1       0  4988.0    0.05       0
  4992.0     0.1       0
Bank Sta=4988,4992
Exp/Cntr=0.3,0.1

Type RM Length L Ch R = 1,4267,458,458,458
BEGIN DESCRIPTION:
Stream0100 9.0
END DESCRIPTION:
XS GIS Cut Line= 3
      1780533.71     13907777.93      1780875.00     13907775.00
      1781174.96     13907725.01
#Sta/Elev= 30
  4654.0 2220.00  4675.3 2218.90  4805.3 2215.52  4825.3 2215.55  4845.3 2214.31
  4935.3 2212.40  4945.3 2211.80  4962.0 2209.80  4975.3 2207.99  4992.8 2204.47
  4997.8 2204.47  5005.4 2202.47  5021.2 2201.83  5021.4 2201.33  5024.9 2201.33
  5025.2 2201.83  5046.0 2203.08  5084.0 2207.86  5089.1 2207.61  5117.0 2209.86
  5137.2 2210.79  5146.7 2211.60  5177.8 2213.44  5205.7 2215.22  5218.3 2215.61
  5266.5 2219.54  5271.6 2219.45  5279.2 2220.63  5296.9 2222.43  5299.4 2222.43
#Mann=6,-1,0
  4654.0    0.07       0  4962.0     0.1       0  5021.2    0.05       0
  5025.2     0.1       0  5146.7    0.07       0  5177.8     0.1       0
Bank Sta=5021.2,5025.2
Exp/Cntr=0.3,0.1

Type RM Length L Ch R = 1,3809,431,431,431
BEGIN DESCRIPTION:
Stream0100 8.0
END DESCRIPTION:
XS GIS Cut Line= 3
      1780524.95     13908124.99      1780825.00     13908175.00
      1781124.98     13908125.00
#Sta/Elev= 30
  4687.7 2218.22  4776.5 2211.48  4781.5 2211.65  4799.3 2210.33  4829.7 2209.11
  4850.0 2207.67  4898.1 2206.14  4958.9 2203.30  4964.0 2203.63  4971.6 2202.64
  4994.4 2201.78  5002.0 2200.92  5017.8 2200.17  5018.0 2199.67  5021.5 2199.67
  5021.8 2200.17  5024.8 2200.71  5032.4 2200.51  5042.6 2201.23  5073.0 2201.71
  5080.6 2202.94  5093.3 2203.26  5141.4 2206.94  5146.5 2206.84  5164.9 2208.00
  5184.5 2209.69  5207.3 2210.86  5255.5 2214.46  5285.9 2216.25  5296.0 2216.38
#Mann=4,-1,0
  4687.7     0.1       0  5017.8    0.05       0  5021.8     0.1       0
  5164.9    0.07       0
Bank Sta=5017.8,5021.8
Exp/Cntr=0.3,0.1

Type RM Length L Ch R = 1,3378,485,485,485
BEGIN DESCRIPTION:
Stream0100 7.0
END DESCRIPTION:
XS GIS Cut Line= 3
      1780525.03     13908575.00      1780825.00     13908575.00
      1780975.03     13908575.00
#Sta/Elev= 30
  4699.6 2214.40  4702.1 2214.40  4729.6 2212.27  4739.6 2211.69  4759.6 2209.91
  4769.6 2209.80  4779.6 2208.89  4799.6 2207.74  4809.6 2206.54  4829.6 2205.26
  4889.6 2199.94  4909.6 2198.89  4949.6 2196.14  4969.6 2195.14  4979.6 2195.08
  4987.6 2194.65  4987.8 2194.15  4991.3 2194.15  4991.6 2194.65  4997.1 2195.52
  5002.1 2195.52  5009.6 2198.42  5019.6 2200.20  5029.6 2200.89  5089.6 2203.15
  5099.6 2203.76  5119.6 2204.26  5129.6 2205.38  5139.6 2204.90  5149.6 2205.28
#Mann=3,-1,0
  4699.6     0.1       0  4987.6    0.05       0  4991.6     0.1       0
Bank Sta=4987.6,4991.6
Exp/Cntr=0.3,0.1

Type RM Length L Ch R = 1,2893,467,467,467
BEGIN DESCRIPTION:
Stream0100 6.0
END DESCRIPTION:
XS GIS Cut Line= 3
      1780674.96     13909025.00      1780725.00     13909025.00
      1780975.01     13908774.99
#Sta/Elev= 30
  4945.7 2203.90  4948.2 2203.90  4955.7 2202.91  4965.7 2202.04  4975.7 2200.77
  4985.7 2198.79  4993.2 2196.12  4999.3 2196.12  5009.9 2191.45  5022.0 2191.09
  5022.3 2190.59  5025.8 2190.59  5026.0 2191.09  5038.2 2191.12  5066.4 2194.58
  5080.6 2194.62  5108.9 2195.17  5123.0 2195.93  5137.2 2195.85  5151.3 2195.61
  5207.9 2197.47  5222.0 2197.83  5236.2 2198.05  5250.7 2199.01  5264.4 2199.59
  5292.7 2200.51  5306.9 2201.22  5321.0 2201.39  5345.8 2202.10  5349.3 2202.10
#Mann=4,-1,0
  4945.7     0.1       0  5022.0    0.05       0  5026.0     0.1       0
  5250.7    0.07       0
Bank Sta=5022,5026
Exp/Cntr=0.3,0.1

Type RM Length L Ch R = 1,2426,486,486,486
BEGIN DESCRIPTION:
Stream0100 5.0
END DESCRIPTION:
XS GIS Cut Line= 3
      1780675.04     13909325.00      1781075.00     13909325.00
      1781275.03     13909174.98
#Sta/Elev= 30
  4604.6 2202.14  4674.6 2199.77  4694.6 2198.69  4724.6 2198.54  4754.6 2197.51
  4764.6 2197.66  4794.6 2195.94  4854.6 2195.17  4884.6 2193.52  4934.6 2189.91
  4964.6 2187.03  4994.6 2186.53  5000.1 2186.15  5000.3 2185.65  5003.8 2185.65
  5004.1 2186.15  5007.7 2186.15  5026.4 2189.17  5041.0 2190.93  5091.0 2193.12
  5111.9 2195.48  5154.6 2197.64  5168.1 2198.87  5176.4 2199.08  5191.0 2200.25
  5204.6 2200.36  5211.9 2201.11  5247.3 2202.11  5251.4 2202.77  5254.6 2202.77
#Mann=3,-1,0
  4604.6     0.1       0  5000.1    0.05       0  5004.1     0.1       0
Bank Sta=5000.1,5004.1
Exp/Cntr=0.3,0.1

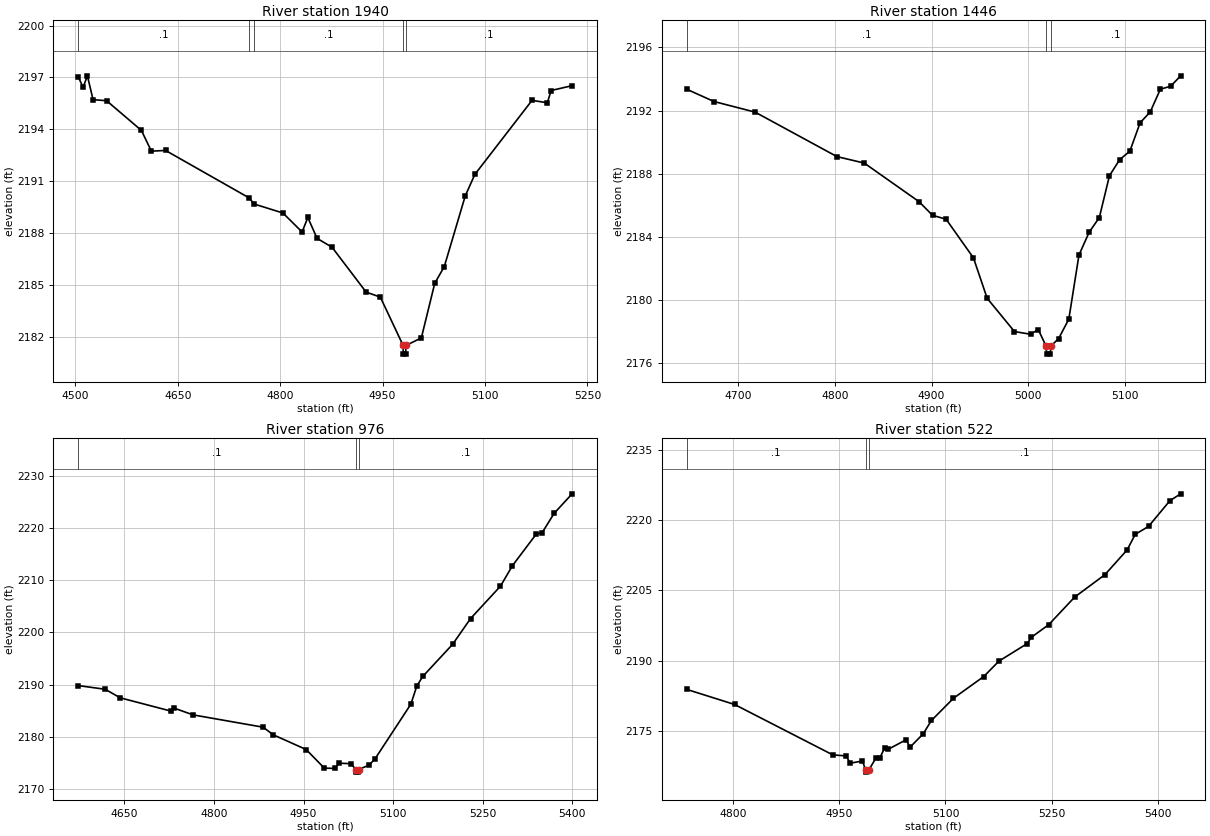
Type RM Length L Ch R = 1,1940,494,494,494
BEGIN DESCRIPTION:
Stream0100 4.0
END DESCRIPTION:
XS GIS Cut Line= 3
      1780774.98     13909474.99      1781175.00     13909775.00
      1781374.98     13909675.01
#Sta/Elev= 30
  4504.0 2197.05  4511.3 2196.42  4517.6 2197.09  4525.9 2195.71  4545.7 2195.65
  4596.7 2193.93  4611.3 2192.73  4632.1 2192.77  4754.7 2190.02  4761.7 2189.67
  4804.0 2189.15  4832.1 2188.05  4840.5 2188.89  4854.0 2187.68  4875.9 2187.17
  4925.9 2184.57  4946.7 2184.28  4980.1 2181.48  4980.3 2180.98  4983.9 2180.98
  4984.2 2181.48  5006.8 2181.92  5026.4 2185.08  5040.4 2186.05  5071.1 2190.14
  5085.1 2191.38  5168.9 2195.67  5191.3 2195.53  5196.9 2196.24  5227.6 2196.52
#Mann=5,-1,0
  4504.0     0.1       0  4754.7    0.07       0  4761.7     0.1       0
  4980.1    0.05       0  4984.2     0.1       0
Bank Sta=4980.1,4984.2
Exp/Cntr=0.3,0.1

Type RM Length L Ch R = 1,1446,470,470,470
BEGIN DESCRIPTION:
Stream0100 3.0
END DESCRIPTION:
XS GIS Cut Line= 3
      1780574.97     13909874.97      1780825.00     13910125.00
      1780974.99     13910175.00
#Sta/Elev= 30
  4646.4 2193.35  4674.7 2192.57  4717.2 2191.90  4802.0 2189.08  4830.3 2188.67
  4886.9 2186.23  4901.0 2185.36  4915.1 2185.11  4943.4 2182.66  4957.6 2180.10
  4985.9 2177.99  5002.6 2177.82  5010.5 2178.12  5018.7 2177.06  5019.1 2176.56
  5023.1 2176.56  5023.4 2177.06  5031.6 2177.54  5042.2 2178.78  5052.7 2182.84
  5063.2 2184.28  5073.8 2185.22  5084.3 2187.87  5094.9 2188.89  5105.4 2189.42
  5116.0 2191.22  5126.5 2191.91  5137.0 2193.35  5147.6 2193.54  5158.1 2194.20
#Mann=3,-1,0
  4646.4     0.1       0  5018.7    0.05       0  5023.4     0.1       0
Bank Sta=5018.7,5023.4
Exp/Cntr=0.3,0.1

Type RM Length L Ch R = 1,976,454,454,454
BEGIN DESCRIPTION:
Stream0100 2.0
END DESCRIPTION:
XS GIS Cut Line= 3
      1780374.98     13910074.96      1780525.00     13910475.00
      1780525.00     13910874.96
#Sta/Elev= 30
  4572.4 2189.85  4617.8 2189.14  4642.8 2187.51  4728.2 2184.96  4733.5 2185.53
  4764.7 2184.25  4882.2 2181.89  4899.1 2180.44  4954.3 2177.62  4984.5 2174.08
  5002.1 2174.00  5009.6 2175.01  5029.6 2174.91  5037.3 2173.80  5037.6 2173.30
  5041.6 2173.30  5042.0 2173.80  5059.6 2174.64  5069.6 2175.84  5129.6 2186.29
  5139.6 2189.78  5149.6 2191.60  5199.6 2197.75  5229.6 2202.67  5279.6 2208.85
  5299.6 2212.76  5339.6 2218.82  5349.6 2219.11  5369.6 2222.79  5399.6 2226.51
#Mann=3,-1,0
  4572.4     0.1       0  5037.3    0.05       0  5042.0     0.1       0
Bank Sta=5037.3,5042
Exp/Cntr=0.3,0.1

Type RM Length L Ch R = 1,522,0,0,0
BEGIN DESCRIPTION:
Stream0100 1.0
END DESCRIPTION:
XS GIS Cut Line= 3
      1780225.02     13910274.96      1780125.00     13910525.00
      1779975.00     13910925.00
#Sta/Elev= 30
  4735.2 2183.91  4802.6 2180.70  4941.2 2169.96  4960.1 2169.74  4965.5 2168.19
  4983.0 2168.66  4987.3 2166.79  4987.6 2166.29  4992.1 2166.79  5001.8 2169.25
  5007.2 2169.25  5014.3 2171.45  5019.6 2171.18  5044.6 2173.19  5049.9 2171.58
  5068.6 2174.44  5080.2 2177.29  5111.3 2182.02  5154.0 2186.65  5175.4 2189.93
  5215.4 2193.68  5220.8 2194.97  5245.7 2197.71  5282.2 2203.57  5324.9 2208.35
  5356.1 2213.61  5367.6 2216.93  5386.3 2218.62  5416.6 2224.12  5431.7 2225.56
#Mann=3,-1,0
  4735.2     0.1       0  4987.3    0.05       0  4992.1     0.1       0
Bank Sta=4987.3,4992.1
Exp/Cntr=0.3,0.1

Chan Stop Cuts=-1