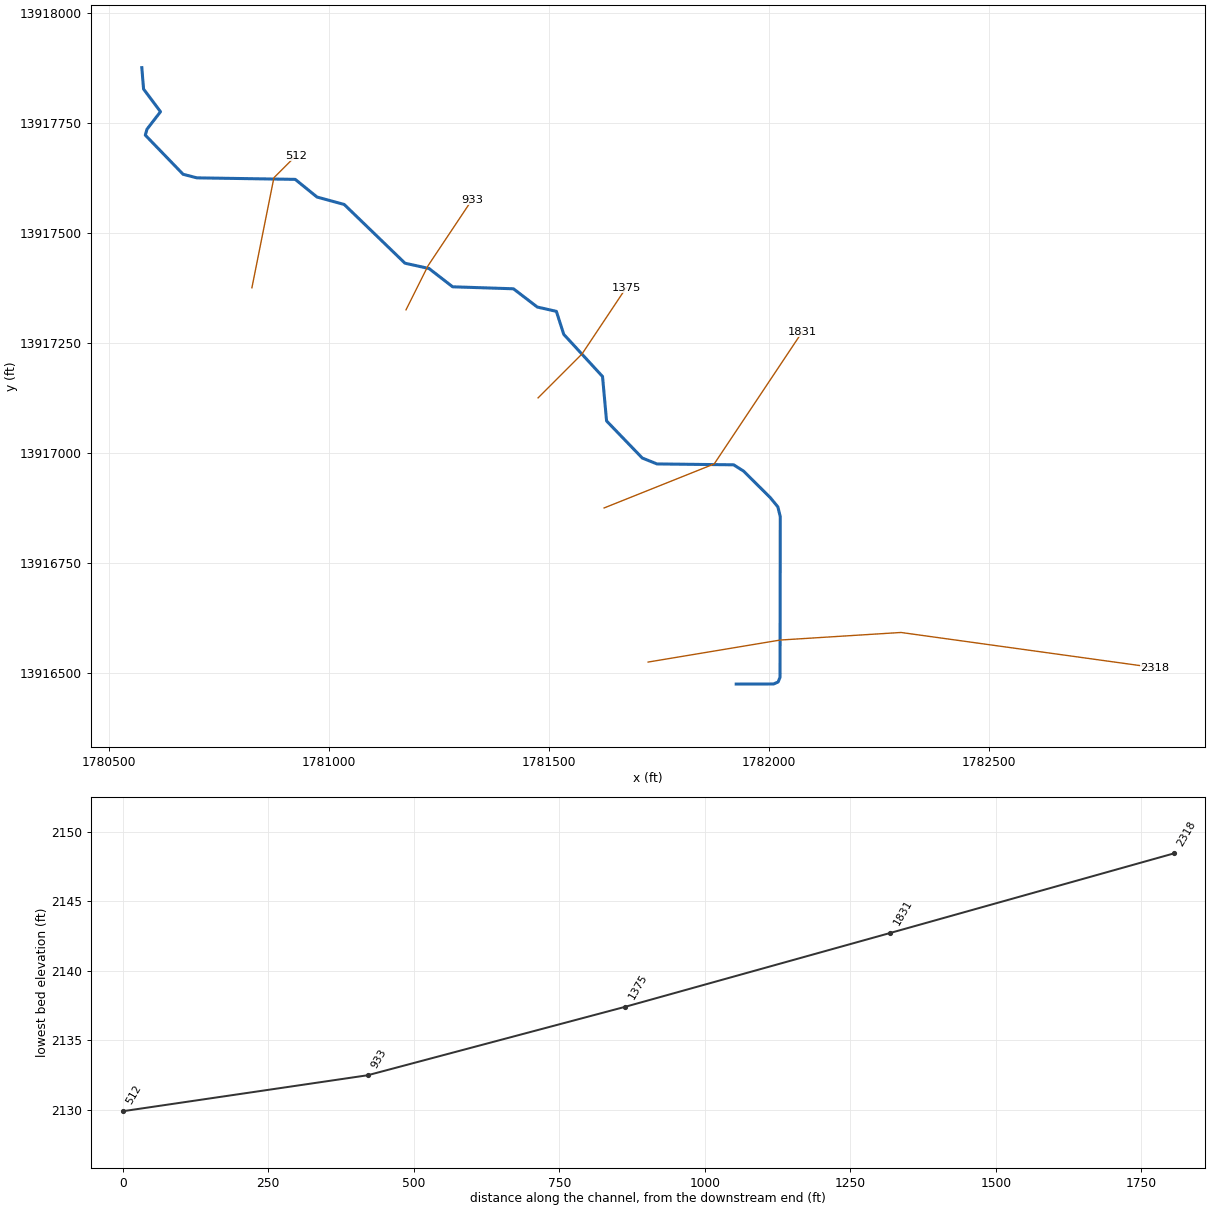
--- Stream0101.prj (project) ---

Proj Title=Stream0101 Base Level Engineering
Current Plan=p01
Default Exp/Contr=0.3,0.1
English Units
Geom File=g01
Flow File=f01
Plan File=p01
BEGIN DESCRIPTION:
Stream0101
END DESCRIPTION:

--- Stream0101.p01 (plan) ---

Plan Title=Multiple Run
Short Identifier=Multiple
Geom File=g01
Flow File=f01
Subcritical Flow
K Sum by GR= 0
Std Step Tol= 0.01
Critical Tol= 0.01
Num of Std Step Trials= 20
Max Error Tol= 0.3
Flow Tol Ratio= 0.001
Split Flow NTrial= 30
Split Flow Tol= 0.02
Split Flow Ratio= 0.02
Log Output Level= 0
Friction Slope Method= 1
Unsteady Friction Slope Method= 2
Unsteady Bridges Friction Slope Method= 1
Parabolic Critical Depth
Global Vel Dist=  1 , 1 , 1
Global Log Level= 0
CheckData=True
Encroach Param= -1, 0, 0, 0
BEGIN DESCRIPTION:
Multiple Run
END DESCRIPTION:

--- Stream0101.f01 (steady flow) ---

Flow Title=Multiple
Number of Profiles=7
Profile Names=10-year,25-year,50-year,1pct_min,100-year,1pct_plu,500-year
River Rch & RM= Stream0101,Reach-1,2318
     737    1233    1694    1127    2248    4485    3910
Boundary for River Rch & Prof#=Stream0101,Reach-1,1
Up Type=0
Dn Type=3
Dn Slope=0.005
Boundary for River Rch & Prof#=Stream0101,Reach-1,2
Up Type=0
Dn Type=3
Dn Slope=0.005
Boundary for River Rch & Prof#=Stream0101,Reach-1,3
Up Type=0
Dn Type=3
Dn Slope=0.005
Boundary for River Rch & Prof#=Stream0101,Reach-1,4
Up Type=0
Dn Type=3
Dn Slope=0.005
Boundary for River Rch & Prof#=Stream0101,Reach-1,5
Up Type=0
Dn Type=3
Dn Slope=0.005
Boundary for River Rch & Prof#=Stream0101,Reach-1,6
Up Type=0
Dn Type=3
Dn Slope=0.005
Boundary for River Rch & Prof#=Stream0101,Reach-1,7
Up Type=0
Dn Type=3
Dn Slope=0.005

--- Stream0101.g01 (geometry) ---

Geom Title=Existing Conditions

River Reach=Stream0101,Reach-1
Reach XY= 30
      1781925.00     13916475.00      1782009.83     13916475.17
      1782020.22     13916479.78      1782024.51     13916490.49
      1782025.04     13916855.02      1782019.55     13916877.47
      1782002.16     13916898.59      1781941.80     13916958.59
      1781919.16     13916972.95      1781744.98     13916974.96
      1781711.65     13916988.36      1781630.52     13917072.56
      1781621.37     13917173.50      1781533.30     13917269.26
      1781516.52     13917321.49      1781473.16     13917331.28
      1781419.09     13917372.76      1781280.93     13917377.25
      1781227.17     13917418.86      1781172.70     13917430.83
      1781034.68     13917564.24      1780972.83     13917581.14
      1780923.45     13917621.25      1780699.87     13917624.70
      1780668.77     13917632.81      1780582.97     13917721.65
      1780586.64     13917734.99      1780617.42     13917774.93
      1780578.98     13917826.36      1780575.00     13917875.00

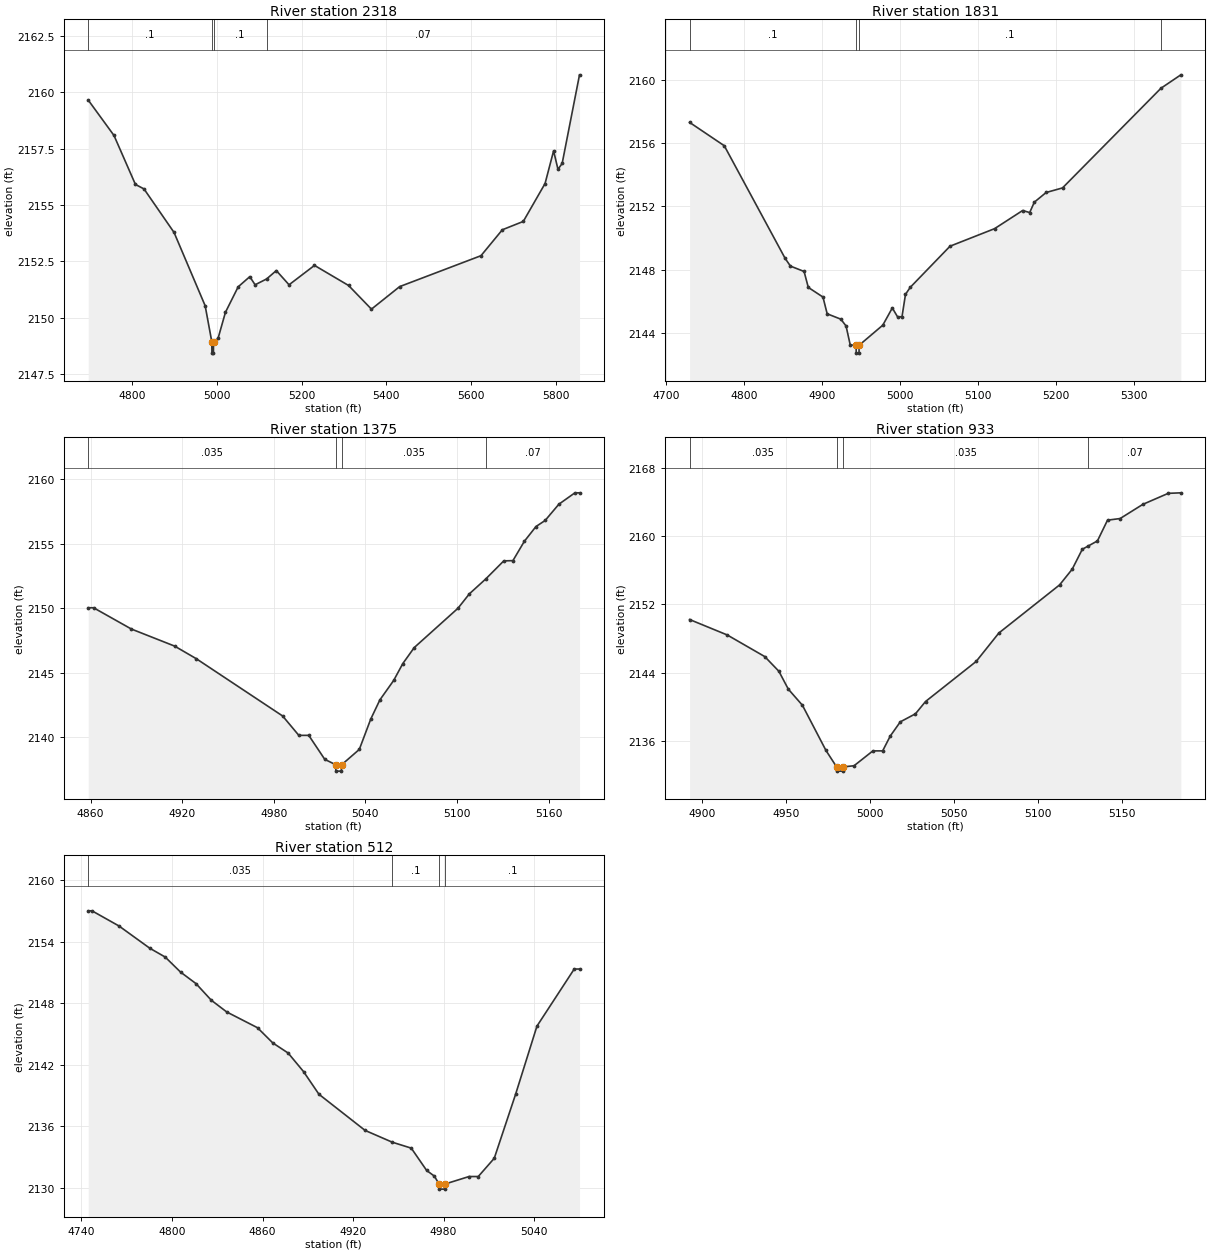
Type RM Length L Ch R = 1,2318,487,487,487
BEGIN DESCRIPTION:
Stream0101 5.0
END DESCRIPTION:
XS GIS Cut Line= 4
      1781724.97     13916524.99      1782025.00     13916575.00
      1782299.15     13916592.20      1782875.58     13916512.33
#Sta/Elev= 30
  4695.7 2159.65  4756.6 2158.08  4807.2 2155.91  4827.5 2155.71  4898.5 2153.78
  4972.0 2150.53  4987.7 2148.93  4988.0 2148.43  4991.5 2148.43  4991.7 2148.93
  5002.4 2149.08  5019.9 2150.24  5050.0 2151.37  5077.4 2151.82  5090.0 2151.46
  5117.3 2151.72  5140.1 2152.09  5170.2 2151.46  5230.3 2152.32  5310.8 2151.43
  5364.9 2150.38  5431.6 2151.38  5623.7 2152.75  5674.2 2153.90  5723.7 2154.27
  5775.1 2155.95  5795.3 2157.40  5805.6 2156.58  5815.5 2156.84  5856.5 2160.77
#Mann=4,-1,0
  4695.7     0.1       0  4987.7    0.05       0  4991.7     0.1       0
  5117.3    0.07       0
Bank Sta=4987.7,4991.7
Exp/Cntr=0.3,0.1

Type RM Length L Ch R = 1,1831,456,456,456
BEGIN DESCRIPTION:
Stream0101 4.0
END DESCRIPTION:
XS GIS Cut Line= 3
      1781624.98     13916874.99      1781875.00     13916975.00
      1782074.98     13917274.97
#Sta/Elev= 30
  4730.2 2157.32  4774.7 2155.84  4852.7 2148.71  4859.5 2148.22  4877.0 2147.88
  4882.4 2146.87  4901.2 2146.26  4906.6 2145.20  4924.1 2144.86  4930.8 2144.43
  4936.2 2143.22  4943.6 2143.21  4943.9 2142.71  4947.4 2142.71  4947.6 2143.21
  4977.9 2144.48  4990.1 2145.57  4996.8 2145.01  5002.5 2145.01  5007.0 2146.43
  5013.0 2146.87  5064.1 2149.48  5121.2 2150.59  5157.2 2151.74  5166.2 2151.61
  5172.2 2152.27  5187.3 2152.88  5208.3 2153.17  5334.5 2159.48  5360.0 2160.33
#Mann=4,-1,0
  4730.2     0.1       0  4943.6    0.05       0  4947.6     0.1       0
  5334.5    0.07       0
Bank Sta=4943.6,4947.6
Exp/Cntr=0.3,0.1

Type RM Length L Ch R = 1,1375,442,442,442
BEGIN DESCRIPTION:
Stream0101 3.0
END DESCRIPTION:
XS GIS Cut Line= 3
      1781475.00     13917125.00      1781575.00     13917225.00
      1781675.00     13917375.00
#Sta/Elev= 30
  4858.5 2150.04  4862.0 2150.04  4886.8 2148.39  4915.1 2147.07  4929.2 2146.10
  4985.8 2141.66  4996.4 2140.16  5002.9 2140.16  5013.4 2138.30  5020.5 2137.89
  5020.7 2137.39  5024.2 2137.39  5024.5 2137.89  5036.0 2139.07  5043.5 2141.42
  5049.5 2142.91  5058.5 2144.41  5064.5 2145.72  5072.0 2146.96  5100.6 2150.00
  5108.1 2151.12  5118.8 2152.27  5130.6 2153.67  5136.6 2153.69  5144.1 2155.19
  5151.7 2156.33  5157.7 2156.80  5166.7 2158.06  5177.2 2158.94  5180.2 2158.94
#Mann=4,-1,0
  4858.5   0.035       0  5020.5   0.035       0  5024.5   0.035       0
  5118.8    0.07       0
Bank Sta=5020.5,5024.5
Exp/Cntr=0.3,0.1

Type RM Length L Ch R = 1,933,421,421,421
BEGIN DESCRIPTION:
Stream0101 2.0
END DESCRIPTION:
XS GIS Cut Line= 3
      1781175.00     13917325.00      1781225.00     13917425.00
      1781325.01     13917575.02
#Sta/Elev= 30
  4892.8 2150.22  4915.2 2148.41  4937.5 2145.88  4945.9 2144.16  4951.5 2142.07
  4959.9 2140.18  4973.9 2134.89  4980.2 2132.97  4980.5 2132.47  4984.0 2132.47
  4984.2 2132.97  4990.6 2133.10  5001.8 2134.84  5007.6 2134.84  5012.1 2136.57
  5018.1 2138.24  5027.1 2139.18  5033.1 2140.62  5063.2 2145.31  5076.7 2148.64
  5112.8 2154.27  5120.3 2156.11  5126.3 2158.44  5129.6 2158.80  5135.3 2159.42
  5141.3 2161.85  5148.8 2162.04  5162.3 2163.70  5177.4 2164.99  5184.9 2165.05
#Mann=4,-1,0
  4892.8   0.035       0  4980.2   0.035       0  4984.2   0.035       0
  5129.6    0.07       0
Bank Sta=4980.2,4984.2
Exp/Cntr=0.3,0.1

Type RM Length L Ch R = 1,512,0,0,0
BEGIN DESCRIPTION:
Stream0101 1.0
END DESCRIPTION:
XS GIS Cut Line= 3
      1780825.01     13917375.03      1780875.00     13917625.00
      1780924.98     13917674.98
#Sta/Elev= 30
  4744.5 2157.04  4747.0 2157.04  4764.9 2155.56  4785.3 2153.39  4795.5 2152.53
  4805.7 2151.06  4815.9 2149.94  4826.1 2148.31  4836.3 2147.17  4856.7 2145.63
  4866.8 2144.15  4877.0 2143.16  4887.2 2141.35  4897.4 2139.14  4928.0 2135.61
  4946.0 2134.46  4958.6 2133.88  4968.8 2131.70  4973.9 2131.15  4977.0 2130.38
  4977.3 2129.88  4980.8 2129.88  4981.0 2130.38  4996.9 2131.11  5003.0 2131.11
  5013.6 2132.89  5027.7 2139.12  5041.9 2145.79  5066.6 2151.36  5070.1 2151.36
#Mann=4,-1,0
  4744.5   0.035       0  4946.0     0.1       0  4977.0    0.05       0
  4981.0     0.1       0
Bank Sta=4977,4981
Exp/Cntr=0.3,0.1

Chan Stop Cuts=-1