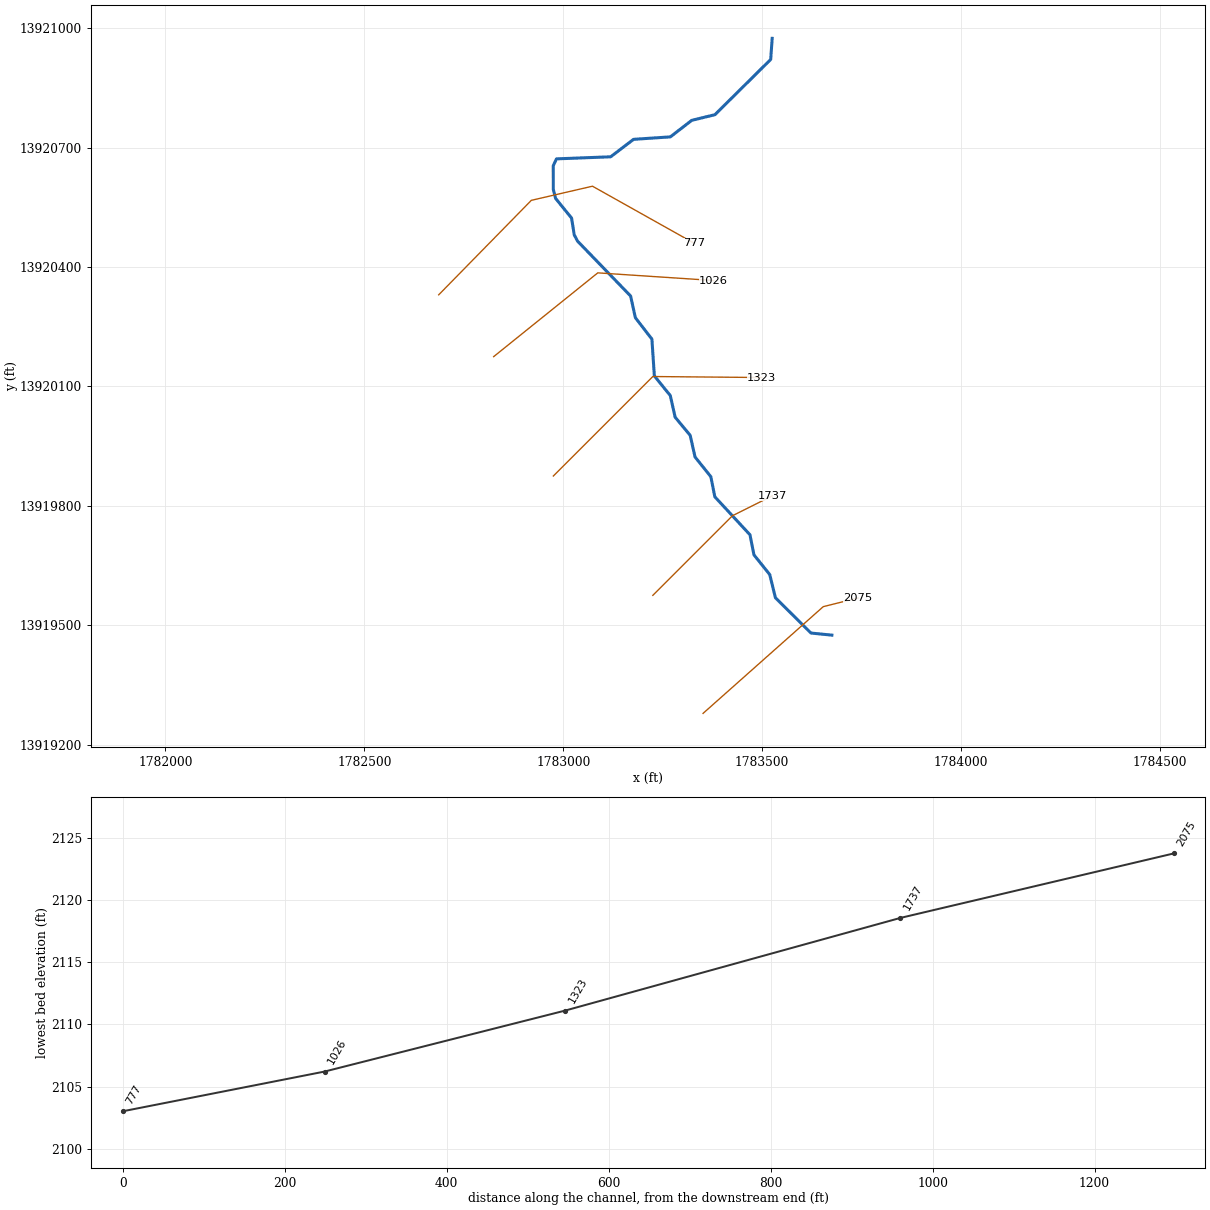
--- Stream0102.prj (project) ---

Proj Title=Stream0102 Base Level Engineering
Current Plan=p01
Default Exp/Contr=0.3,0.1
English Units
Geom File=g01
Flow File=f01
Plan File=p01
BEGIN DESCRIPTION:
Stream0102
END DESCRIPTION:

--- Stream0102.p01 (plan) ---

Plan Title=Multiple Run
Short Identifier=Multiple
Geom File=g01
Flow File=f01
Subcritical Flow
K Sum by GR= 0
Std Step Tol= 0.01
Critical Tol= 0.01
Num of Std Step Trials= 20
Max Error Tol= 0.3
Flow Tol Ratio= 0.001
Split Flow NTrial= 30
Split Flow Tol= 0.02
Split Flow Ratio= 0.02
Log Output Level= 0
Friction Slope Method= 1
Unsteady Friction Slope Method= 2
Unsteady Bridges Friction Slope Method= 1
Parabolic Critical Depth
Global Vel Dist=  1 , 1 , 1
Global Log Level= 0
CheckData=True
Encroach Param= -1, 0, 0, 0
BEGIN DESCRIPTION:
Multiple Run
END DESCRIPTION:

--- Stream0102.f01 (steady flow) ---

Flow Title=Multiple
Number of Profiles=7
Profile Names=10-year,25-year,50-year,1pct_min,100-year,1pct_plu,500-year
River Rch & RM= Stream0102,Reach-1,2075
     455     741    1002     657    1311    2615    2212
Boundary for River Rch & Prof#=Stream0102,Reach-1,1
Up Type=0
Dn Type=3
Dn Slope=0.005
Boundary for River Rch & Prof#=Stream0102,Reach-1,2
Up Type=0
Dn Type=3
Dn Slope=0.005
Boundary for River Rch & Prof#=Stream0102,Reach-1,3
Up Type=0
Dn Type=3
Dn Slope=0.005
Boundary for River Rch & Prof#=Stream0102,Reach-1,4
Up Type=0
Dn Type=3
Dn Slope=0.005
Boundary for River Rch & Prof#=Stream0102,Reach-1,5
Up Type=0
Dn Type=3
Dn Slope=0.005
Boundary for River Rch & Prof#=Stream0102,Reach-1,6
Up Type=0
Dn Type=3
Dn Slope=0.005
Boundary for River Rch & Prof#=Stream0102,Reach-1,7
Up Type=0
Dn Type=3
Dn Slope=0.005

--- Stream0102.g01 (geometry) ---

Geom Title=Existing Conditions

River Reach=Stream0102,Reach-1
Reach XY= 30
      1783675.00     13919475.00      1783622.46     13919480.30
      1783533.13     13919568.93      1783518.90     13919627.19
      1783479.19     13919676.73      1783469.15     13919727.29
      1783380.85     13919822.71      1783370.81     13919873.26
      1783331.08     13919922.80      1783318.92     13919977.20
      1783281.08     13920022.80      1783268.88     13920077.18
      1783228.83     13920126.58      1783222.67     13920219.03
      1783181.14     13920272.83      1783169.17     13920327.30
      1783035.76     13920465.32      1783027.49     13920481.03
      1783020.77     13920523.26      1782980.62     13920572.74
      1782974.81     13920595.27      1782974.77     13920654.99
      1782982.85     13920672.06      1783119.05     13920677.27
      1783176.60     13920721.14      1783269.04     13920727.33
      1783322.83     13920768.87      1783381.08     13920783.09
      1783521.21     13920921.86      1783525.00     13920975.00

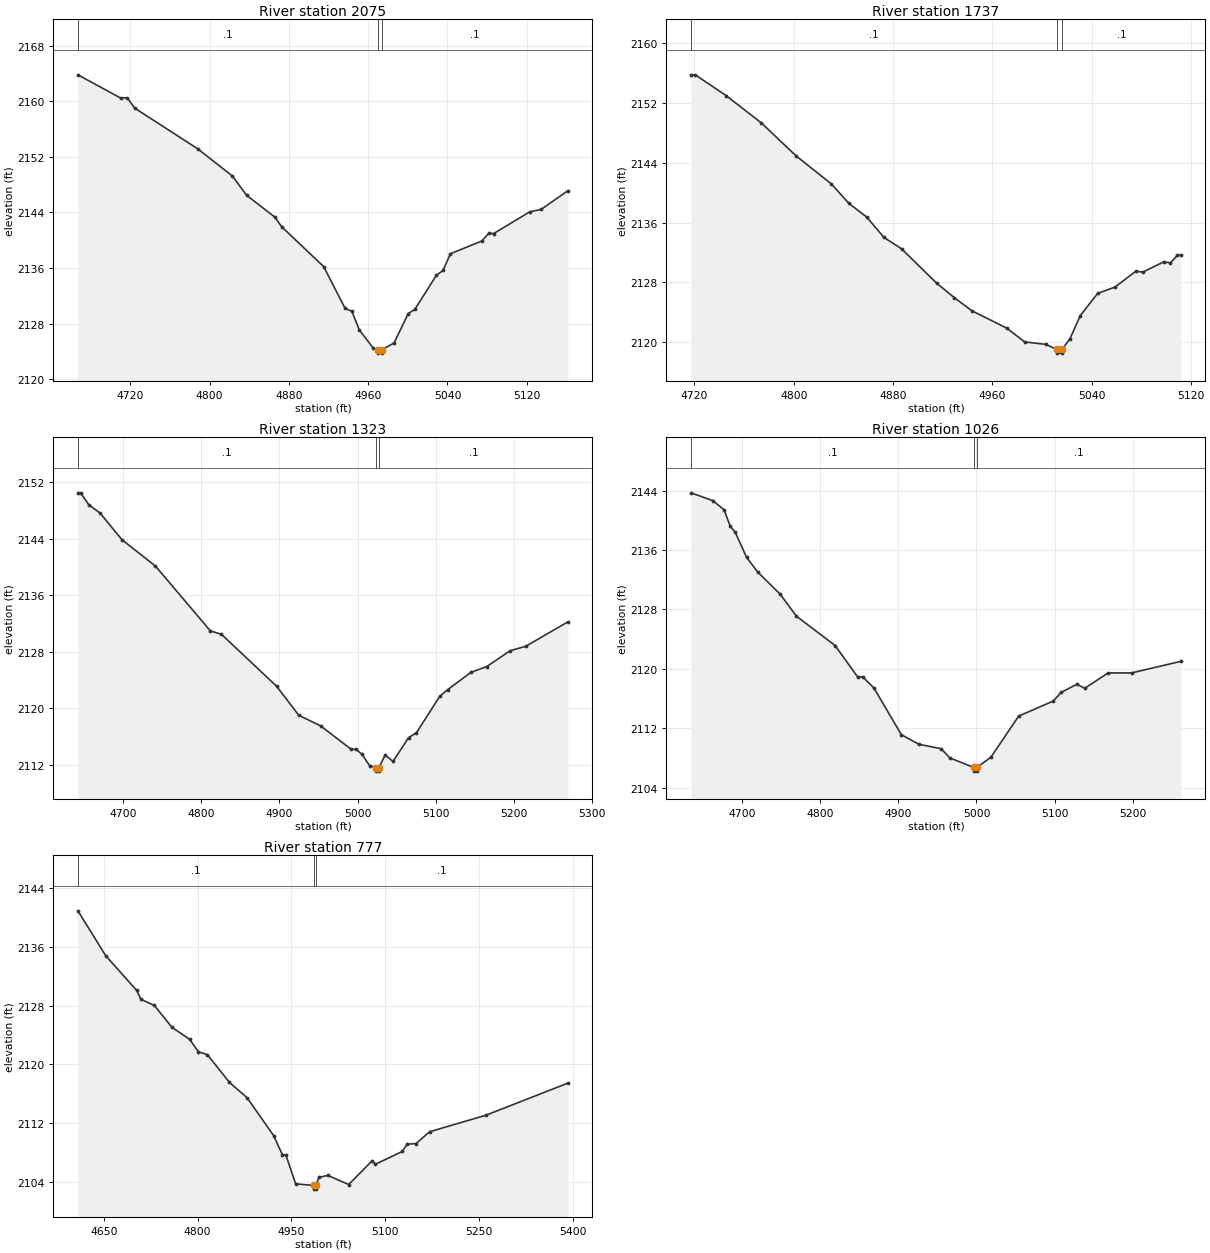
Type RM Length L Ch R = 1,2075,338,338,338
BEGIN DESCRIPTION:
Stream0102 4.0
END DESCRIPTION:
XS GIS Cut Line= 3
      1783351.29     13919278.38      1783653.32     13919546.61
      1783740.99     13919568.48
#Sta/Elev= 30
  4667.2 2163.79  4710.2 2160.46  4716.9 2160.49  4724.4 2159.01  4788.0 2153.15
  4823.1 2149.23  4837.3 2146.47  4865.8 2143.33  4872.8 2141.93  4915.1 2136.20
  4936.8 2130.18  4943.5 2129.78  4951.1 2127.09  4965.3 2124.44  4970.0 2124.25
  4970.2 2123.75  4973.7 2123.75  4974.0 2124.25  4986.2 2125.22  5000.4 2129.44
  5007.1 2130.04  5028.8 2134.94  5035.5 2135.64  5043.0 2138.05  5074.6 2139.88
  5081.6 2140.97  5086.7 2140.96  5122.9 2144.07  5134.7 2144.44  5161.5 2147.12
#Mann=3,-1,0
  4667.2     0.1       0  4970.0    0.05       0  4974.0     0.1       0
Bank Sta=4970,4974
Exp/Cntr=0.3,0.1

Type RM Length L Ch R = 1,1737,414,414,414
BEGIN DESCRIPTION:
Stream0102 3.0
END DESCRIPTION:
XS GIS Cut Line= 3
      1783225.02     13919575.02      1783425.00     13919775.00
      1783524.98     13919824.99
#Sta/Elev= 30
  4717.2 2155.72  4720.7 2155.72  4745.5 2152.95  4773.7 2149.33  4802.0 2144.88
  4830.3 2141.15  4844.5 2138.54  4858.6 2136.75  4872.7 2134.00  4886.9 2132.48
  4915.2 2127.88  4929.3 2125.97  4943.4 2124.22  4971.7 2121.88  4985.9 2120.06
  5002.8 2119.73  5012.0 2119.06  5012.2 2118.56  5015.7 2118.56  5016.0 2119.06
  5022.4 2120.47  5030.8 2123.57  5044.7 2126.53  5058.7 2127.38  5075.5 2129.50
  5081.1 2129.38  5097.8 2130.73  5103.4 2130.62  5109.0 2131.62  5111.8 2131.62
#Mann=3,-1,0
  4717.2     0.1       0  5012.0    0.05       0  5016.0     0.1       0
Bank Sta=5012,5016
Exp/Cntr=0.3,0.1

Type RM Length L Ch R = 1,1323,297,297,297
BEGIN DESCRIPTION:
Stream0102 2.0
END DESCRIPTION:
XS GIS Cut Line= 3
      1782974.99     13919874.99      1783225.00     13920125.00
      1783499.02     13920122.48
#Sta/Elev= 30
  4641.8 2150.46  4645.3 2150.46  4656.0 2148.73  4670.1 2147.61  4698.4 2143.81
  4740.8 2140.14  4811.5 2130.94  4825.7 2130.45  4896.4 2123.10  4924.7 2119.01
  4952.9 2117.49  4991.8 2114.20  4997.9 2114.20  5005.4 2113.53  5015.4 2111.88
  5023.4 2111.61  5023.6 2111.11  5027.1 2111.11  5027.4 2111.61  5035.4 2113.39
  5045.4 2112.48  5065.4 2115.85  5075.4 2116.53  5105.4 2121.70  5115.4 2122.63
  5145.4 2125.09  5165.4 2125.89  5195.4 2128.13  5215.4 2128.76  5269.4 2132.21
#Mann=3,-1,0
  4641.8     0.1       0  5023.4    0.05       0  5027.4     0.1       0
Bank Sta=5023.4,5027.4
Exp/Cntr=0.3,0.1

Type RM Length L Ch R = 1,1026,249,249,249
BEGIN DESCRIPTION:
Stream0102 1.0
END DESCRIPTION:
XS GIS Cut Line= 3
      1782824.99     13920174.99      1783086.66     13920385.57
      1783378.05     13920366.31
#Sta/Elev= 30
  4634.1 2143.72  4662.1 2142.67  4676.5 2141.44  4684.5 2139.21  4690.9 2138.41
  4705.3 2135.04  4719.7 2133.04  4748.5 2130.05  4769.3 2127.09  4818.9 2123.14
  4847.7 2118.91  4854.1 2118.92  4868.5 2117.43  4903.7 2111.13  4926.1 2109.83
  4954.8 2109.23  4965.7 2108.00  4996.4 2106.71  4996.6 2106.21  5000.1 2106.21
  5000.4 2106.71  5018.4 2108.07  5054.0 2113.62  5098.6 2115.67  5108.6 2116.83
  5128.7 2117.92  5138.7 2117.37  5168.7 2119.44  5198.8 2119.45  5262.0 2121.01
#Mann=3,-1,0
  4634.1     0.1       0  4996.4    0.05       0  5000.4     0.1       0
Bank Sta=4996.4,5000.4
Exp/Cntr=0.3,0.1

Type RM Length L Ch R = 1,777,0,0,0
BEGIN DESCRIPTION:
Stream0102 0.0
END DESCRIPTION:
XS GIS Cut Line= 4
      1782686.85     13920330.36      1782919.66     13920567.84
      1783073.35     13920603.34      1783329.44     13920459.73
#Sta/Elev= 30
  4608.5 2140.91  4652.9 2134.81  4702.4 2130.08  4709.5 2128.85  4730.6 2128.05
  4758.9 2125.06  4787.2 2123.42  4801.4 2121.70  4815.5 2121.34  4850.9 2117.56
  4879.2 2115.46  4921.7 2110.30  4935.6 2107.70  4941.1 2107.70  4956.8 2103.74
  4985.6 2103.52  4985.8 2103.02  4989.3 2103.02  4989.6 2103.52  4993.9 2104.61
  5008.1 2104.89  5041.8 2103.65  5079.4 2106.90  5084.5 2106.41  5127.7 2108.16
  5135.1 2109.14  5149.4 2109.22  5171.1 2110.83  5261.2 2113.08  5392.4 2117.45
#Mann=3,-1,0
  4608.5     0.1       0  4985.6    0.05       0  4989.6     0.1       0
Bank Sta=4985.6,4989.6
Exp/Cntr=0.3,0.1

Chan Stop Cuts=-1