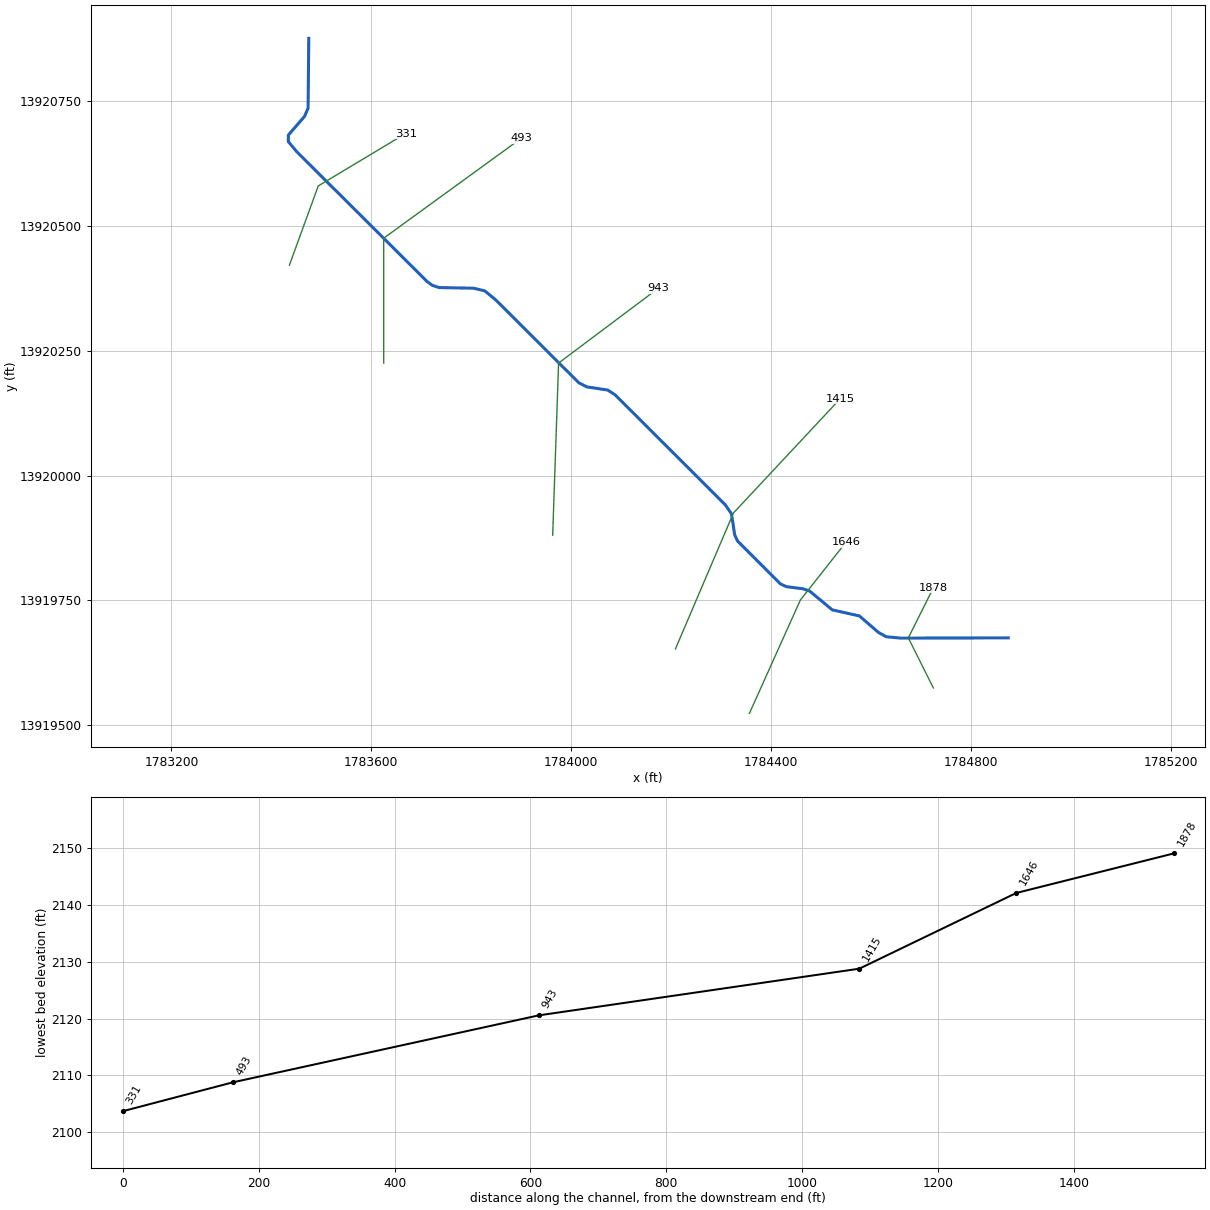
--- Stream0103.prj (project) ---

Proj Title=Stream0103 Base Level Engineering
Current Plan=p01
Default Exp/Contr=0.3,0.1
English Units
Geom File=g01
Flow File=f01
Plan File=p01
BEGIN DESCRIPTION:
Stream0103
END DESCRIPTION:

--- Stream0103.p01 (plan) ---

Plan Title=Multiple Run
Short Identifier=Multiple
Geom File=g01
Flow File=f01
Subcritical Flow
K Sum by GR= 0
Std Step Tol= 0.01
Critical Tol= 0.01
Num of Std Step Trials= 20
Max Error Tol= 0.3
Flow Tol Ratio= 0.001
Split Flow NTrial= 30
Split Flow Tol= 0.02
Split Flow Ratio= 0.02
Log Output Level= 0
Friction Slope Method= 1
Unsteady Friction Slope Method= 2
Unsteady Bridges Friction Slope Method= 1
Parabolic Critical Depth
Global Vel Dist=  1 , 1 , 1
Global Log Level= 0
CheckData=True
Encroach Param= -1, 0, 0, 0
BEGIN DESCRIPTION:
Multiple Run
END DESCRIPTION:

--- Stream0103.f01 (steady flow) ---

Flow Title=Multiple
Number of Profiles=7
Profile Names=10-year,25-year,50-year,1pct_min,100-year,1pct_plu,500-year
River Rch & RM= Stream0103,Reach-1,1878
     309     489     648     418     834    1665    1360
Boundary for River Rch & Prof#=Stream0103,Reach-1,1
Up Type=0
Dn Type=3
Dn Slope=0.005
Boundary for River Rch & Prof#=Stream0103,Reach-1,2
Up Type=0
Dn Type=3
Dn Slope=0.005
Boundary for River Rch & Prof#=Stream0103,Reach-1,3
Up Type=0
Dn Type=3
Dn Slope=0.005
Boundary for River Rch & Prof#=Stream0103,Reach-1,4
Up Type=0
Dn Type=3
Dn Slope=0.005
Boundary for River Rch & Prof#=Stream0103,Reach-1,5
Up Type=0
Dn Type=3
Dn Slope=0.005
Boundary for River Rch & Prof#=Stream0103,Reach-1,6
Up Type=0
Dn Type=3
Dn Slope=0.005
Boundary for River Rch & Prof#=Stream0103,Reach-1,7
Up Type=0
Dn Type=3
Dn Slope=0.005

--- Stream0103.g01 (geometry) ---

Geom Title=Existing Conditions

River Reach=Stream0103,Reach-1
Reach XY= 30
      1784875.00     13919675.00      1784659.82     13919674.56
      1784630.93     13919677.24      1784615.33     13919685.80
      1784577.18     13919718.88      1784522.80     13919731.08
      1784477.18     13919768.90      1784464.29     13919773.30
      1784431.03     13919777.50      1784418.93     13919783.13
      1784333.15     13919868.93      1784327.53     13919881.04
      1784321.02     13919923.35      1784308.35     13919941.67
      1784088.21     13920161.37      1784073.35     13920171.02
      1784031.05     13920177.53      1784015.32     13920185.78
      1783848.52     13920352.12      1783827.43     13920369.48
      1783804.94     13920374.87      1783735.48     13920376.17
      1783722.57     13920380.52      1783711.70     13920388.40
      1783450.72     13920648.31      1783434.12     13920668.26
      1783434.28     13920681.53      1783466.53     13920718.80
      1783473.65     13920735.41      1783475.00     13920875.00

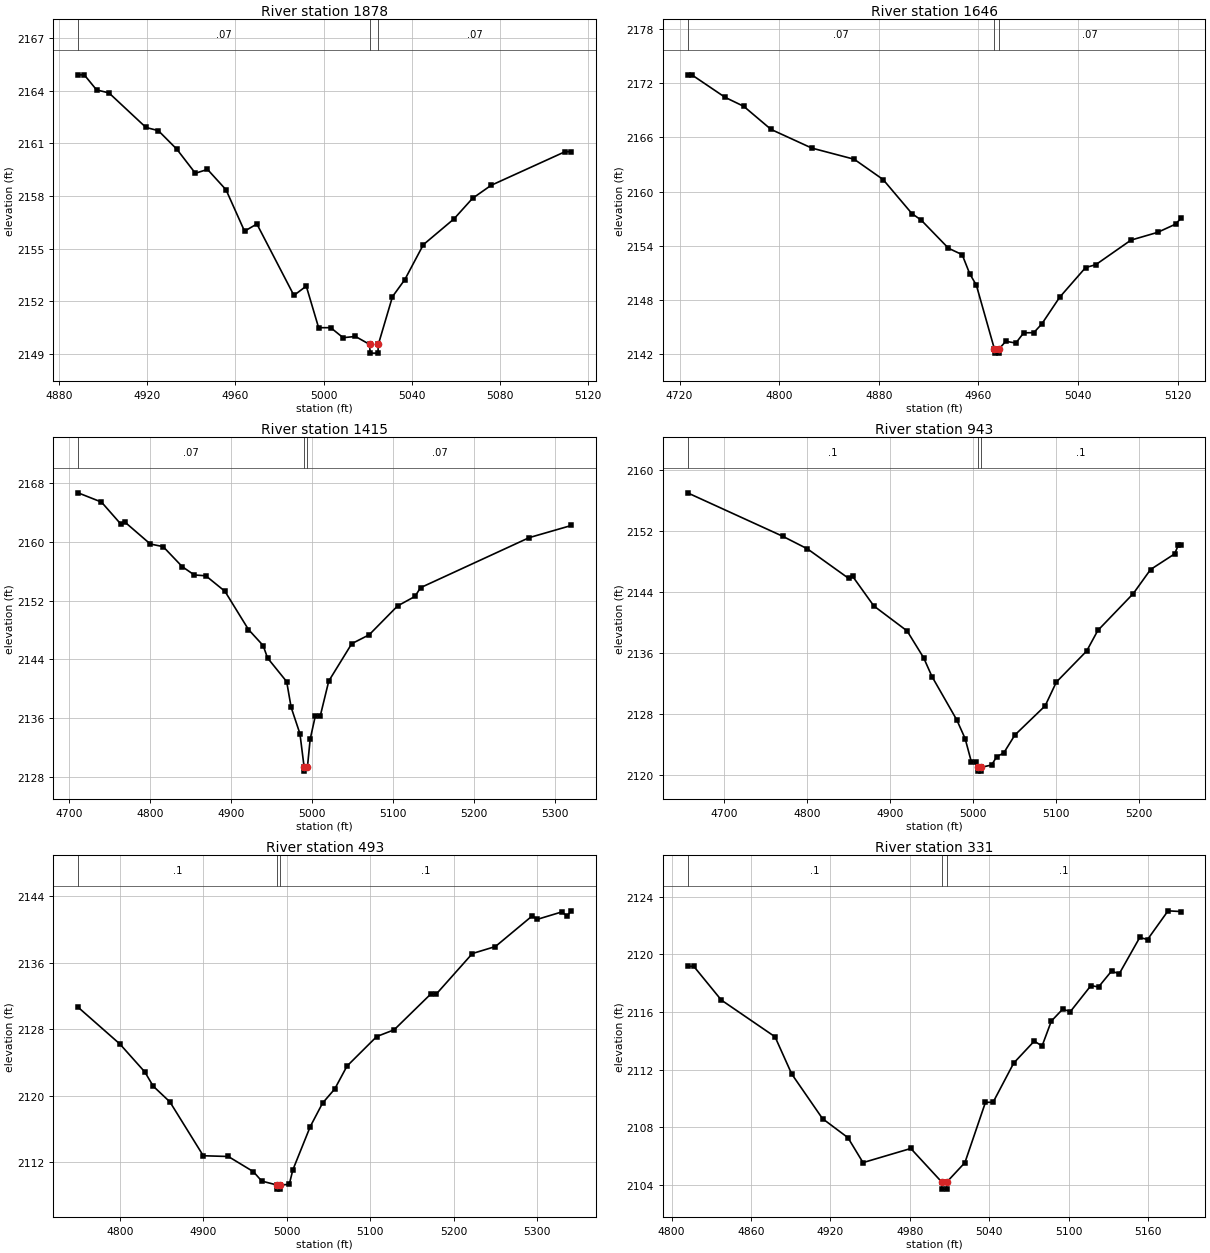
Type RM Length L Ch R = 1,1878,232,232,232
BEGIN DESCRIPTION:
Stream0103 4.0
END DESCRIPTION:
XS GIS Cut Line= 3
      1784725.02     13919574.96      1784675.00     13919675.00
      1784725.02     13919775.04
#Sta/Elev= 30
  4888.6 2164.90  4891.4 2164.90  4897.0 2164.04  4902.6 2163.87  4919.4 2161.90
  4925.0 2161.72  4933.4 2160.66  4941.8 2159.29  4947.3 2159.51  4955.7 2158.35
  4964.1 2155.99  4969.7 2156.40  4986.5 2152.33  4992.1 2152.86  4997.7 2150.49
  5003.2 2150.49  5008.8 2149.92  5014.4 2149.99  5020.8 2149.54  5021.1 2149.04
  5024.6 2149.04  5024.8 2149.54  5031.2 2152.26  5036.8 2153.23  5045.2 2155.22
  5059.1 2156.69  5067.5 2157.86  5075.9 2158.60  5109.5 2160.52  5112.3 2160.52
#Mann=3,-1,0
  4888.6    0.07       0  5020.8    0.05       0  5024.8    0.07       0
Bank Sta=5020.8,5024.8
Exp/Cntr=0.3,0.1

Type RM Length L Ch R = 1,1646,231,231,231
BEGIN DESCRIPTION:
Stream0103 3.1
END DESCRIPTION:
XS GIS Cut Line= 3
      1784356.95     13919523.90      1784458.91     13919750.72
      1784550.11     13919866.41
#Sta/Elev= 30
  4726.4 2172.94  4729.8 2172.94  4756.6 2170.44  4771.5 2169.45  4793.4 2166.89
  4826.1 2164.82  4860.2 2163.58  4883.4 2161.33  4906.5 2157.56  4914.0 2156.83
  4935.9 2153.71  4946.9 2153.00  4952.9 2150.90  4958.3 2149.61  4972.7 2142.58
  4972.9 2142.08  4976.4 2142.08  4976.7 2142.58  4981.9 2143.39  4990.0 2143.20
  4996.3 2144.33  5004.4 2144.35  5010.8 2145.31  5025.2 2148.28  5046.0 2151.57
  5054.1 2151.88  5082.4 2154.61  5103.8 2155.47  5118.2 2156.38  5122.4 2157.01
#Mann=3,-1,0
  4726.4    0.07       0  4972.7    0.05       0  4976.7    0.07       0
Bank Sta=4972.7,4976.7
Exp/Cntr=0.3,0.1

Type RM Length L Ch R = 1,1415,472,472,472
BEGIN DESCRIPTION:
Stream0103 3.0
END DESCRIPTION:
XS GIS Cut Line= 3
      1784208.90     13919652.93      1784325.00     13919925.00
      1784539.10     13920153.99
#Sta/Elev= 30
  4710.7 2166.68  4739.6 2165.42  4763.2 2162.46  4768.6 2162.69  4799.9 2159.71
  4815.8 2159.35  4839.4 2156.62  4854.3 2155.49  4868.5 2155.38  4892.1 2153.27
  4921.2 2148.06  4939.3 2145.88  4944.8 2144.18  4968.4 2140.96  4973.9 2137.47
  4984.8 2133.86  4990.0 2129.27  4990.2 2128.77  4994.0 2129.27  4997.4 2133.10
  5003.8 2136.29  5009.9 2136.29  5020.4 2141.04  5048.8 2146.13  5070.3 2147.34
  5105.4 2151.27  5126.9 2152.57  5133.8 2153.76  5268.1 2160.58  5320.0 2162.23
#Mann=3,-1,0
  4710.7    0.07       0  4990.0    0.05       0  4994.0    0.07       0
Bank Sta=4990,4994
Exp/Cntr=0.3,0.1

Type RM Length L Ch R = 1,943,450,450,450
BEGIN DESCRIPTION:
Stream0103 2.0
END DESCRIPTION:
XS GIS Cut Line= 3
      1783963.21     13919880.49      1783975.00     13920225.00
      1784174.99     13920374.99
#Sta/Elev= 30
  4655.6 2157.00  4770.2 2151.32  4800.2 2149.66  4849.7 2145.81  4854.7 2146.06
  4880.2 2142.19  4920.3 2138.92  4940.3 2135.40  4950.3 2132.95  4980.3 2127.25
  4990.3 2124.82  4997.8 2121.78  5003.4 2121.78  5005.6 2121.06  5005.9 2120.56
  5009.4 2120.56  5009.6 2121.06  5022.2 2121.36  5028.4 2122.45  5036.8 2122.93
  5050.3 2125.29  5086.8 2129.11  5100.3 2132.22  5136.8 2136.28  5150.3 2138.98
  5193.0 2143.80  5213.9 2146.96  5243.0 2149.01  5247.2 2150.13  5250.3 2150.13
#Mann=3,-1,0
  4655.6     0.1       0  5005.6    0.05       0  5009.6     0.1       0
Bank Sta=5005.6,5009.6
Exp/Cntr=0.3,0.1

Type RM Length L Ch R = 1,493,162,162,162
BEGIN DESCRIPTION:
Stream0103 1.0
END DESCRIPTION:
XS GIS Cut Line= 3
      1783625.00     13920225.05      1783625.00     13920475.00
      1783900.87     13920675.35
#Sta/Elev= 30
  4750.1 2130.64  4800.1 2126.23  4830.1 2122.86  4840.1 2121.16  4860.1 2119.27
  4900.1 2112.80  4930.1 2112.71  4960.1 2110.89  4970.1 2109.76  4988.1 2109.29
  4988.3 2108.79  4991.8 2108.79  4992.1 2109.29  5003.1 2109.36  5007.4 2111.10
  5028.3 2116.31  5043.0 2119.12  5057.6 2120.82  5072.3 2123.57  5107.9 2127.12
  5128.8 2127.93  5172.8 2132.24  5179.0 2132.19  5222.5 2137.09  5250.1 2137.93
  5294.2 2141.61  5300.4 2141.20  5329.7 2142.09  5335.9 2141.60  5341.0 2142.22
#Mann=3,-1,0
  4750.1     0.1       0  4988.1    0.05       0  4992.1     0.1       0
Bank Sta=4988.1,4992.1
Exp/Cntr=0.3,0.1

Type RM Length L Ch R = 1,331,0,0,0
BEGIN DESCRIPTION:
Stream0103 0.0
END DESCRIPTION:
XS GIS Cut Line= 3
      1783436.27     13920421.06      1783493.94     13920579.57
      1783668.91     13920684.52
#Sta/Elev= 30
  4812.1 2119.17  4816.8 2119.17  4837.6 2116.83  4878.2 2114.28  4890.8 2111.70
  4914.1 2108.60  4933.3 2107.28  4944.7 2105.55  4980.8 2106.53  5004.1 2104.21
  5004.4 2103.71  5007.9 2103.71  5008.1 2104.21  5021.7 2105.55  5037.2 2109.73
  5043.0 2109.74  5058.6 2112.46  5074.1 2113.98  5080.0 2113.64  5087.0 2115.37
  5095.5 2116.19  5101.4 2116.03  5116.9 2117.83  5122.7 2117.74  5132.5 2118.84
  5138.3 2118.65  5153.8 2121.17  5159.7 2121.03  5175.2 2123.02  5184.8 2122.97
#Mann=3,-1,0
  4812.1     0.1       0  5004.1    0.05       0  5008.1     0.1       0
Bank Sta=5004.1,5008.1
Exp/Cntr=0.3,0.1

Chan Stop Cuts=-1