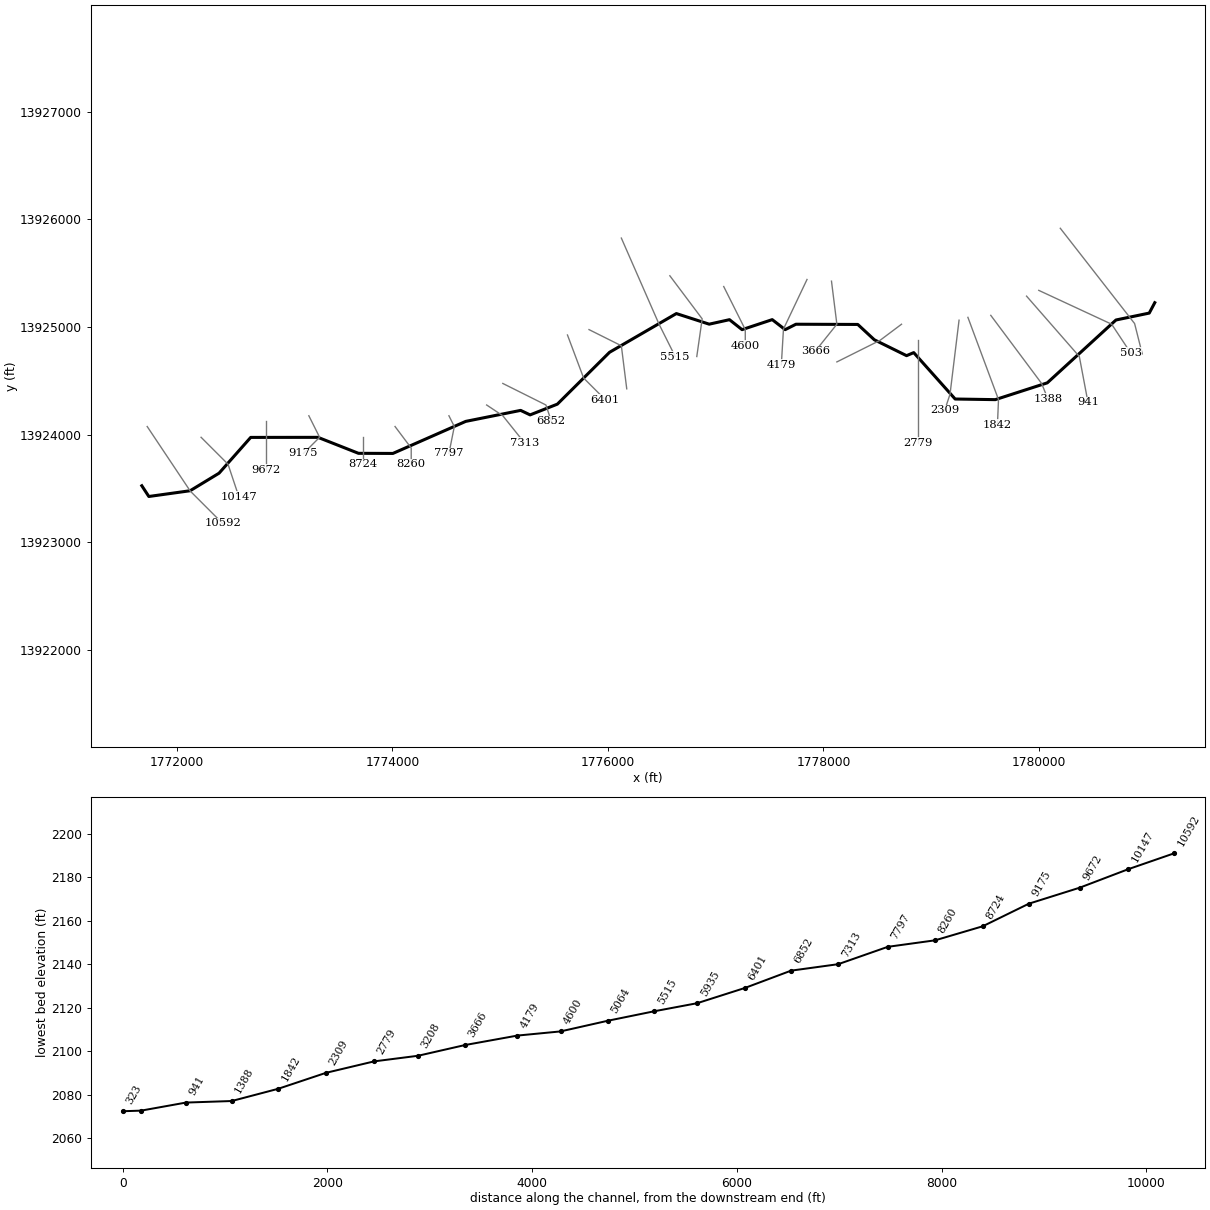
--- Stream0104.prj (project) ---

Proj Title=Stream0104 Base Level Engineering
Current Plan=p01
Default Exp/Contr=0.3,0.1
English Units
Geom File=g01
Flow File=f01
Plan File=p01
BEGIN DESCRIPTION:
Stream0104
END DESCRIPTION:

--- Stream0104.p01 (plan) ---

Plan Title=Multiple Run
Short Identifier=Multiple
Geom File=g01
Flow File=f01
Subcritical Flow
K Sum by GR= 0
Std Step Tol= 0.01
Critical Tol= 0.01
Num of Std Step Trials= 20
Max Error Tol= 0.3
Flow Tol Ratio= 0.001
Split Flow NTrial= 30
Split Flow Tol= 0.02
Split Flow Ratio= 0.02
Log Output Level= 0
Friction Slope Method= 1
Unsteady Friction Slope Method= 2
Unsteady Bridges Friction Slope Method= 1
Parabolic Critical Depth
Global Vel Dist=  1 , 1 , 1
Global Log Level= 0
CheckData=True
Encroach Param= -1, 0, 0, 0
BEGIN DESCRIPTION:
Multiple Run
END DESCRIPTION:

--- Stream0104.f01 (steady flow) ---

Flow Title=Multiple
Number of Profiles=7
Profile Names=10-year,25-year,50-year,1pct_min,100-year,1pct_plu,500-year
River Rch & RM= Stream0104,Reach-1,10592
    1156    1992    2794    1892    3776    7533    6820
River Rch & RM= Stream0104,Reach-1,8260
    1310    2270    3195    2171    4331    8642    7875
River Rch & RM= Stream0104,Reach-1,5064
    1942    3441    4916    3385    6755   13477   12624
River Rch & RM= Stream0104,Reach-1,4600
    2374    4239    6085    4207    8394   16749   15819
Boundary for River Rch & Prof#=Stream0104,Reach-1,1
Up Type=0
Dn Type=3
Dn Slope=0.005
Boundary for River Rch & Prof#=Stream0104,Reach-1,2
Up Type=0
Dn Type=3
Dn Slope=0.005
Boundary for River Rch & Prof#=Stream0104,Reach-1,3
Up Type=0
Dn Type=3
Dn Slope=0.005
Boundary for River Rch & Prof#=Stream0104,Reach-1,4
Up Type=0
Dn Type=3
Dn Slope=0.005
Boundary for River Rch & Prof#=Stream0104,Reach-1,5
Up Type=0
Dn Type=3
Dn Slope=0.005
Boundary for River Rch & Prof#=Stream0104,Reach-1,6
Up Type=0
Dn Type=3
Dn Slope=0.005
Boundary for River Rch & Prof#=Stream0104,Reach-1,7
Up Type=0
Dn Type=3
Dn Slope=0.005

--- Stream0104.g01 (geometry) ---

Geom Title=Existing Conditions

River Reach=Stream0104,Reach-1
Reach XY= 30
      1771675.00     13923525.00      1771740.06     13923425.30
      1772123.45     13923478.75      1772391.71     13923641.64
      1772685.43     13923973.95      1773309.78     13923974.48
      1773685.50     13923826.22      1774004.97     13923825.07
      1774680.93     13924122.76      1775190.42     13924224.85
      1775278.31     13924183.07      1775531.17     13924282.86
      1776015.32     13924764.24      1776635.44     13925123.96
      1776940.22     13925025.49      1777128.41     13925067.19
      1777245.13     13924974.61      1777525.10     13925067.67
      1777645.13     13924974.61      1777745.03     13925024.91
      1778319.15     13925022.94      1778472.57     13924880.52
      1778771.67     13924733.02      1778838.33     13924761.35
      1779222.55     13924330.46      1779595.15     13924324.64
      1780077.43     13924480.52      1780715.02     13925064.32
      1781023.74     13925128.38      1781075.00     13925225.00

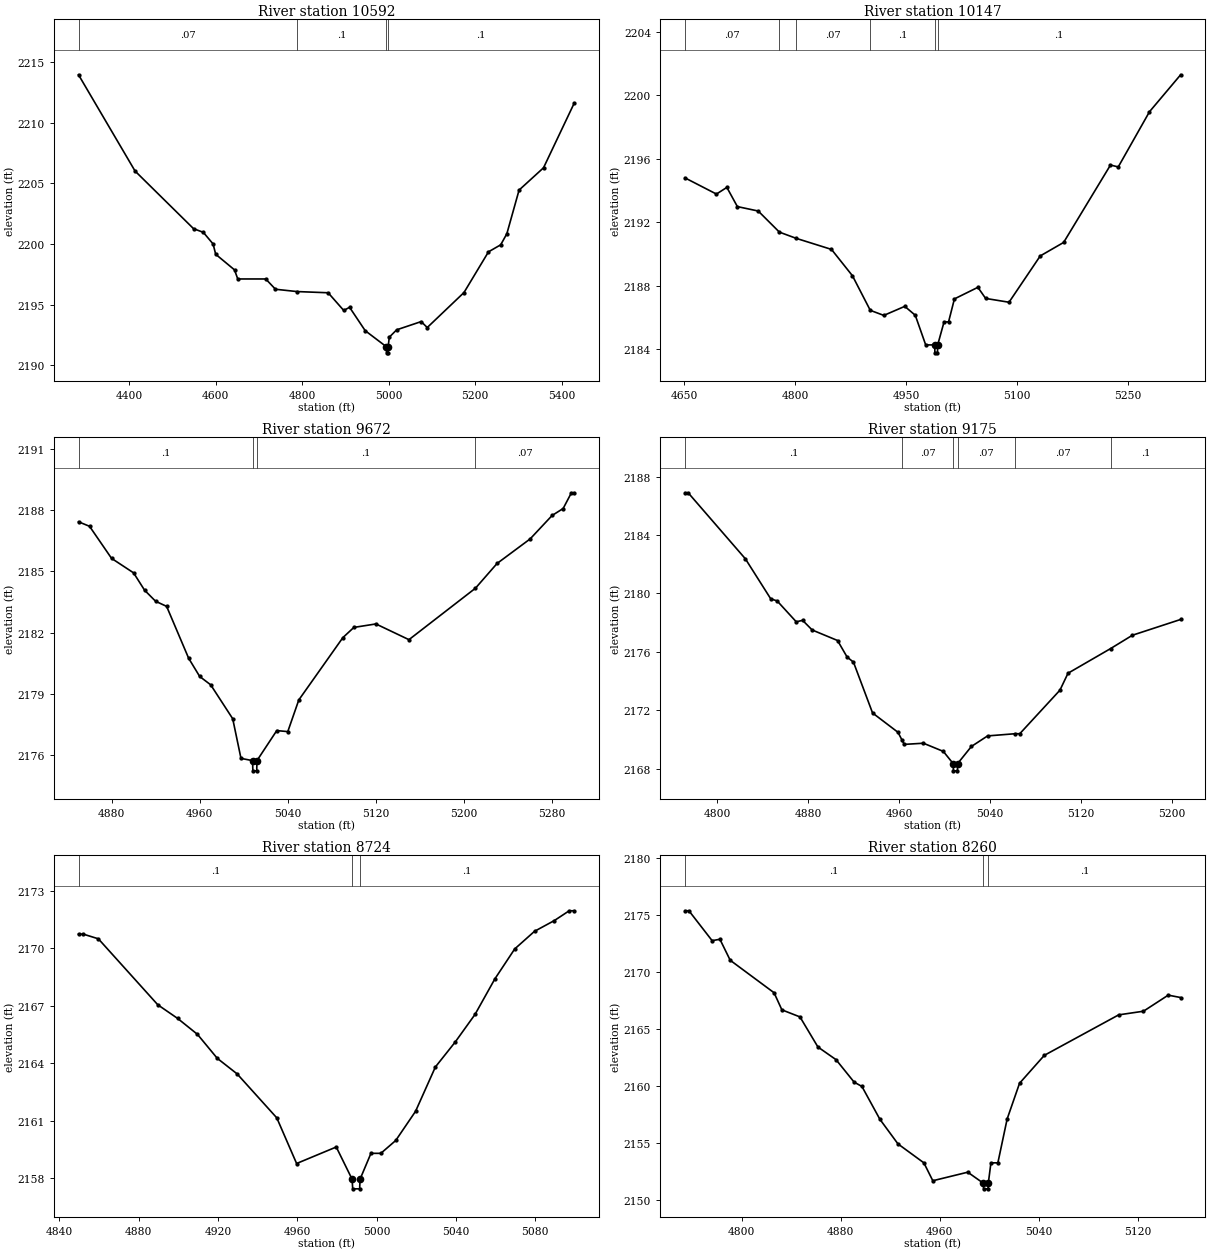
Type RM Length L Ch R = 1,10592,445,445,445
BEGIN DESCRIPTION:
Stream0104 23.0
END DESCRIPTION:
XS GIS Cut Line= 3
      1771725.01     13924074.98      1772125.00     13923475.00
      1772425.03     13923174.97
#Sta/Elev= 30
  4283.1 2213.97  4413.8 2206.02  4549.0 2201.26  4571.5 2200.96  4594.1 2200.00
  4600.1 2199.15  4643.6 2197.86  4651.1 2197.11  4715.7 2197.11  4738.3 2196.26
  4787.9 2196.07  4860.0 2195.97  4896.0 2194.51  4909.5 2194.77  4945.6 2192.84
  4994.7 2191.51  4994.9 2191.01  4998.4 2191.01  4998.7 2191.51  5001.2 2192.30
  5018.3 2192.91  5074.9 2193.59  5089.0 2193.10  5173.9 2195.99  5230.5 2199.35
  5258.7 2199.93  5272.9 2200.84  5301.2 2204.45  5357.7 2206.29  5428.5 2211.62
#Mann=4,-1,0
  4283.1    0.07       0  4787.9     0.1       0  4994.7    0.05       0
  4998.7     0.1       0
Bank Sta=4994.7,4998.7
Exp/Cntr=0.3,0.1

Type RM Length L Ch R = 1,10147,475,475,475
BEGIN DESCRIPTION:
Stream0104 22.0
END DESCRIPTION:
XS GIS Cut Line= 3
      1772224.97     13923975.03      1772475.00     13923725.00
      1772574.99     13923425.03
#Sta/Elev= 30
  4651.2 2194.79  4693.7 2193.77  4707.8 2194.19  4722.0 2192.98  4750.2 2192.70
  4778.8 2191.37  4801.4 2190.98  4849.2 2190.28  4877.5 2188.62  4901.6 2186.44
  4919.9 2186.12  4948.2 2186.69  4962.4 2186.13  4976.5 2184.26  4988.7 2184.26
  4988.9 2183.76  4992.4 2183.76  4992.7 2184.26  5001.3 2185.71  5007.4 2185.71
  5015.3 2187.16  5047.0 2187.89  5057.5 2187.19  5089.1 2186.95  5131.3 2189.87
  5162.9 2190.72  5226.2 2195.60  5236.7 2195.48  5278.9 2198.96  5321.0 2201.29
#Mann=6,-1,0
  4651.2    0.07       0  4778.8     0.1       0  4801.4    0.07       0
  4901.6     0.1       0  4988.7    0.05       0  4992.7     0.1       0
Bank Sta=4988.7,4992.7
Exp/Cntr=0.3,0.1

Type RM Length L Ch R = 1,9672,497,497,497
BEGIN DESCRIPTION:
Stream0104 21.0
END DESCRIPTION:
XS GIS Cut Line= 3
      1772825.00     13924125.03      1772825.00     13923975.00
      1772825.00     13923675.03
#Sta/Elev= 30
  4850.0 2187.42  4860.0 2187.20  4880.0 2185.63  4900.0 2184.92  4910.0 2184.07
  4920.0 2183.53  4930.0 2183.28  4950.0 2180.74  4960.0 2179.85  4970.0 2179.44
  4990.0 2177.78  4997.5 2175.84  5008.0 2175.73  5008.3 2175.23  5011.8 2175.23
  5012.0 2175.73  5030.0 2177.20  5040.0 2177.15  5050.0 2178.70  5090.0 2181.75
  5100.0 2182.25  5120.0 2182.42  5150.0 2181.65  5210.4 2184.17  5230.0 2185.38
  5260.0 2186.58  5280.0 2187.73  5290.0 2188.07  5297.5 2188.84  5300.0 2188.84
#Mann=4,-1,0
  4850.0     0.1       0  5008.0    0.05       0  5012.0     0.1       0
  5210.4    0.07       0
Bank Sta=5008,5012
Exp/Cntr=0.3,0.1

Type RM Length L Ch R = 1,9175,451,451,451
BEGIN DESCRIPTION:
Stream0104 20.0
END DESCRIPTION:
XS GIS Cut Line= 3
      1773225.02     13924174.96      1773325.00     13923975.00
      1773175.00     13923825.00
#Sta/Elev= 30
  4771.9 2186.89  4774.7 2186.89  4825.0 2182.37  4847.3 2179.63  4852.9 2179.49
  4869.7 2178.06  4875.3 2178.16  4883.7 2177.50  4906.0 2176.78  4914.4 2175.65
  4920.0 2175.30  4936.8 2171.82  4959.1 2170.50  4962.6 2169.98  4964.7 2169.67
  4981.5 2169.75  4999.0 2169.19  5007.6 2168.36  5007.9 2167.86  5011.4 2167.86
  5011.6 2168.36  5023.7 2169.53  5037.9 2170.25  5062.1 2170.40  5066.2 2170.40
  5101.5 2173.38  5108.6 2174.54  5146.1 2176.23  5165.2 2177.14  5207.6 2178.22
#Mann=6,-1,0
  4771.9     0.1       0  4962.6    0.07       0  5007.6    0.05       0
  5011.6    0.07       0  5062.1    0.07       0  5146.1     0.1       0
Bank Sta=5007.6,5011.6
Exp/Cntr=0.3,0.1

Type RM Length L Ch R = 1,8724,464,464,464
BEGIN DESCRIPTION:
Stream0104 19.0
END DESCRIPTION:
XS GIS Cut Line= 3
      1773725.00     13923975.01      1773725.00     13923825.00
      1773725.00     13923725.01
#Sta/Elev= 28
  4849.6 2170.73  4852.1 2170.73  4859.6 2170.49  4889.6 2167.05  4899.6 2166.34
  4909.6 2165.51  4919.6 2164.26  4929.6 2163.45  4949.6 2161.16  4959.6 2158.78
  4979.6 2159.64  4987.6 2157.96  4987.9 2157.46  4991.4 2157.46  4991.6 2157.96
  4997.1 2159.31  5002.1 2159.31  5009.6 2159.98  5019.6 2161.50  5029.6 2163.81
  5039.6 2165.11  5049.6 2166.55  5059.6 2168.40  5069.6 2169.96  5079.6 2170.88
  5089.6 2171.44  5097.1 2171.95  5099.6 2171.95
#Mann=3,-1,0
  4849.6     0.1       0  4987.6    0.05       0  4991.6     0.1       0
Bank Sta=4987.6,4991.6
Exp/Cntr=0.3,0.1

Type RM Length L Ch R = 1,8260,463,463,463
BEGIN DESCRIPTION:
Stream0104 18.0
END DESCRIPTION:
XS GIS Cut Line= 3
      1774024.97     13924075.04      1774175.00     13923875.00
      1774175.00     13923725.05
#Sta/Elev= 30
  4754.3 2175.40  4757.5 2175.40  4776.2 2172.78  4782.5 2172.90  4790.8 2171.06
  4826.2 2168.21  4832.5 2166.71  4847.1 2166.09  4861.6 2163.45  4876.2 2162.34
  4890.8 2160.37  4897.1 2159.99  4911.6 2157.11  4926.2 2154.95  4947.1 2153.29
  4954.3 2151.72  4982.5 2152.47  4995.0 2151.51  4995.3 2151.01  4998.9 2151.01
  4999.1 2151.51  5001.2 2153.29  5006.8 2153.29  5014.3 2157.14  5024.3 2160.27
  5044.3 2162.72  5104.3 2166.27  5124.3 2166.59  5144.3 2168.00  5154.3 2167.79
#Mann=3,-1,0
  4754.3     0.1       0  4995.0    0.05       0  4999.1     0.1       0
Bank Sta=4995,4999.1
Exp/Cntr=0.3,0.1

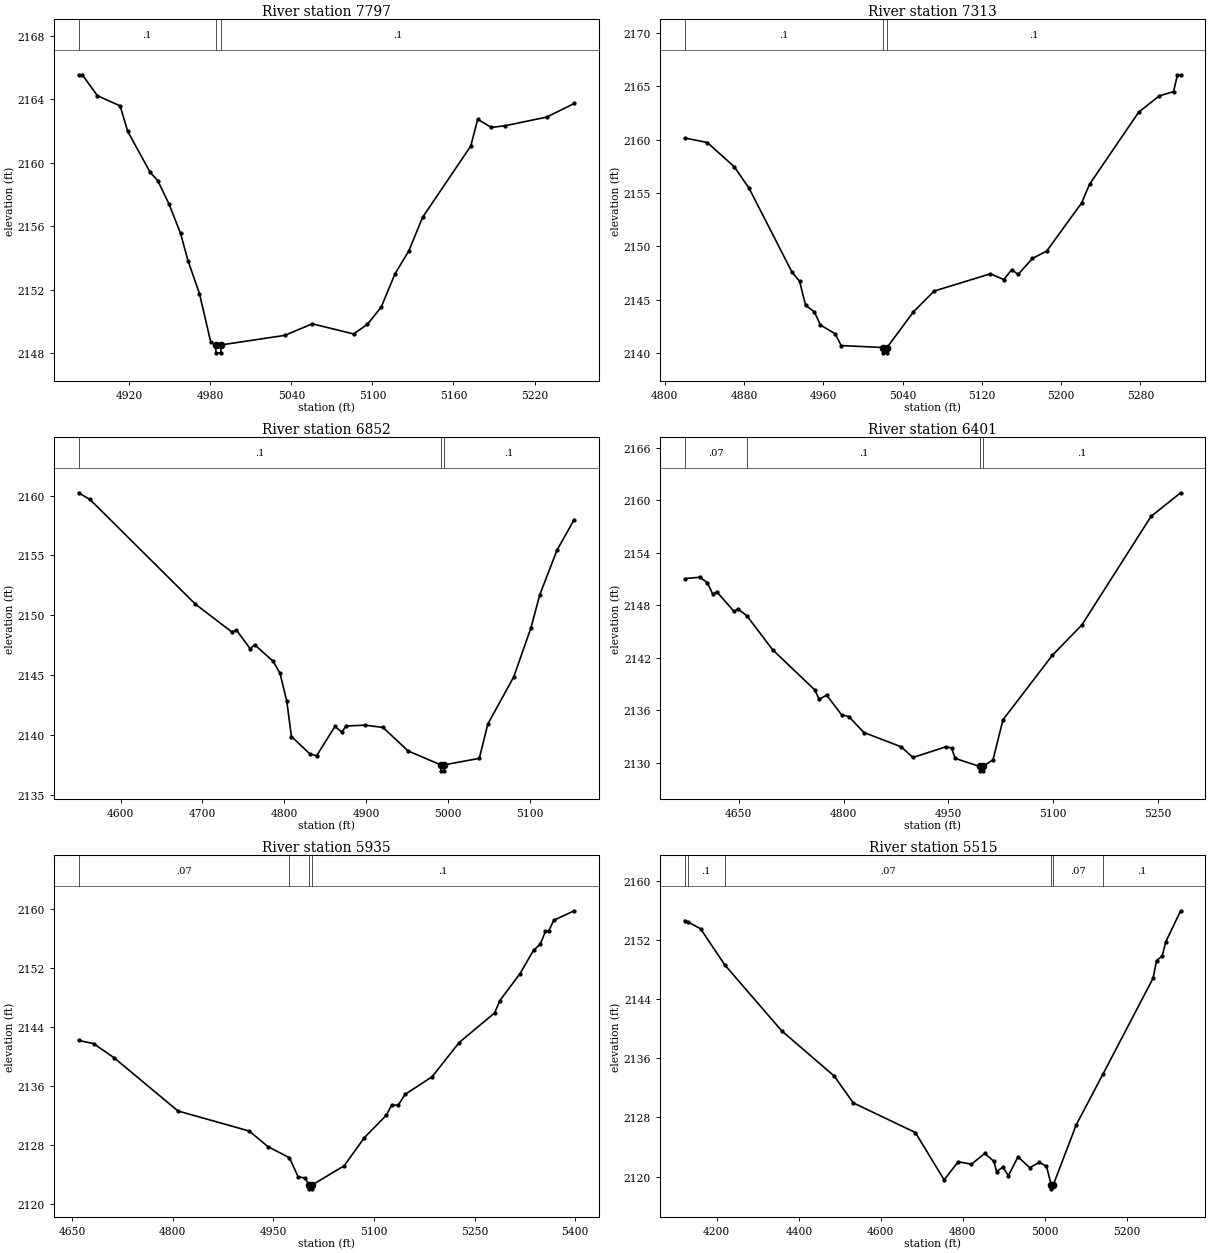
Type RM Length L Ch R = 1,7797,484,484,484
BEGIN DESCRIPTION:
Stream0104 17.0
END DESCRIPTION:
XS GIS Cut Line= 3
      1774524.98     13924175.04      1774575.00     13924075.00
      1774525.00     13923825.00
#Sta/Elev= 30
  4882.5 2165.54  4885.3 2165.54  4896.5 2164.22  4913.3 2163.58  4918.9 2161.97
  4935.6 2159.38  4941.2 2158.86  4949.6 2157.37  4958.0 2155.54  4963.6 2153.80
  4972.0 2151.75  4980.4 2148.67  4983.9 2148.51  4984.2 2148.01  4987.8 2148.01
  4988.0 2148.51  5035.1 2149.11  5055.5 2149.84  5086.1 2149.20  5096.3 2149.81
  5106.5 2150.89  5116.7 2152.99  5126.9 2154.43  5137.1 2156.55  5172.8 2161.05
  5177.9 2162.73  5188.1 2162.22  5198.3 2162.33  5228.9 2162.87  5249.3 2163.73
#Mann=3,-1,0
  4882.5     0.1       0  4983.9    0.05       0  4988.0     0.1       0
Bank Sta=4983.9,4988
Exp/Cntr=0.3,0.1

Type RM Length L Ch R = 1,7313,461,461,461
BEGIN DESCRIPTION:
Stream0104 16.0
END DESCRIPTION:
XS GIS Cut Line= 3
      1774875.00     13924275.00      1775025.00     13924175.00
      1775224.98     13923925.02
#Sta/Elev= 30
  4820.3 2160.16  4842.8 2159.74  4869.9 2157.48  4884.9 2155.47  4928.5 2147.56
  4936.0 2146.73  4942.0 2144.50  4951.0 2143.85  4957.0 2142.64  4972.0 2141.80
  4978.0 2140.70  5020.1 2140.52  5020.3 2140.02  5024.0 2140.02  5024.3 2140.52
  5051.0 2143.87  5071.8 2145.81  5128.6 2147.43  5142.2 2146.89  5150.2 2147.82
  5156.6 2147.37  5171.1 2148.87  5185.5 2149.56  5220.7 2154.07  5228.7 2155.82
  5278.3 2162.58  5299.1 2164.11  5313.5 2164.51  5317.5 2166.09  5320.7 2166.09
#Mann=3,-1,0
  4820.3     0.1       0  5020.1    0.05       0  5024.3     0.1       0
Bank Sta=5020.1,5024.3
Exp/Cntr=0.3,0.1

Type RM Length L Ch R = 1,6852,451,451,451
BEGIN DESCRIPTION:
Stream0104 15.0
END DESCRIPTION:
XS GIS Cut Line= 3
      1775024.99     13924475.00      1775425.00     13924275.00
      1775474.99     13924125.04
#Sta/Elev= 30
  4548.6 2160.23  4562.6 2159.67  4691.2 2150.95  4735.9 2148.62  4741.5 2148.78
  4758.2 2147.23  4763.8 2147.55  4786.2 2146.18  4794.6 2145.19  4803.0 2142.83
  4808.6 2139.90  4830.9 2138.47  4839.3 2138.29  4861.7 2140.74  4870.0 2140.28
  4875.6 2140.78  4898.0 2140.85  4920.4 2140.66  4951.1 2138.70  4990.9 2137.54
  4991.2 2137.04  4994.9 2137.04  4995.2 2137.54  5038.0 2138.08  5048.5 2140.95
  5080.2 2144.89  5101.2 2148.98  5111.8 2151.70  5132.9 2155.44  5153.9 2157.99
#Mann=3,-1,0
  4548.6     0.1       0  4990.9    0.05       0  4995.2     0.1       0
Bank Sta=4990.9,4995.2
Exp/Cntr=0.3,0.1

Type RM Length L Ch R = 1,6401,466,466,466
BEGIN DESCRIPTION:
Stream0104 14.0
END DESCRIPTION:
XS GIS Cut Line= 3
      1775625.00     13924924.99      1775775.00     13924525.00
      1775974.97     13924325.03
#Sta/Elev= 30
  4572.8 2151.06  4594.2 2151.21  4604.8 2150.59  4612.8 2149.24  4618.2 2149.56
  4643.1 2147.30  4648.4 2147.60  4661.6 2146.79  4698.3 2142.92  4758.8 2138.32
  4765.0 2137.26  4775.7 2137.72  4797.1 2135.49  4807.8 2135.26  4829.1 2133.45
  4882.5 2131.82  4899.4 2130.60  4946.6 2131.82  4954.6 2131.69  4959.9 2130.49
  4995.1 2129.57  4995.4 2129.07  4999.2 2129.07  4999.5 2129.57  5014.1 2130.34
  5028.3 2134.91  5099.0 2142.28  5141.4 2145.76  5240.4 2158.17  5282.8 2160.87
#Mann=4,-1,0
  4572.8    0.07       0  4661.6     0.1       0  4995.1    0.05       0
  4999.5     0.1       0
Bank Sta=4995.1,4999.5
Exp/Cntr=0.3,0.1

Type RM Length L Ch R = 1,5935,420,420,420
BEGIN DESCRIPTION:
Stream0104 13.0
END DESCRIPTION:
XS GIS Cut Line= 3
      1775824.97     13924975.02      1776125.00     13924825.00
      1776175.00     13924424.96
#Sta/Elev= 30
  4659.8 2142.19  4682.2 2141.76  4712.9 2139.83  4808.0 2132.62  4914.2 2129.90
  4942.1 2127.78  4974.1 2126.28  4986.9 2123.72  4997.8 2123.50  5003.1 2122.56
  5003.4 2122.06  5007.2 2122.06  5007.5 2122.56  5055.7 2125.19  5085.9 2129.02
  5118.7 2132.06  5126.3 2133.40  5136.3 2133.41  5146.4 2134.87  5186.7 2137.26
  5227.0 2141.90  5279.9 2145.92  5287.5 2147.57  5317.7 2151.24  5337.9 2154.43
  5348.0 2155.25  5355.5 2156.97  5360.6 2157.08  5368.1 2158.48  5398.4 2159.77
#Mann=4,-1,0
  4659.8    0.07       0  4974.1     0.1       0  5003.1    0.05       0
  5007.5     0.1       0
Bank Sta=5003.1,5007.5
Exp/Cntr=0.3,0.1

Type RM Length L Ch R = 1,5515,451,451,451
BEGIN DESCRIPTION:
Stream0104 12.0
END DESCRIPTION:
XS GIS Cut Line= 3
      1776124.98     13925825.04      1776475.00     13925025.00
      1776625.02     13924724.97
#Sta/Elev= 30
  4122.4 2154.59  4128.7 2154.41  4160.3 2153.49  4219.3 2148.61  4358.3 2139.69
  4486.1 2133.59  4532.9 2129.95  4684.2 2125.95  4754.3 2119.56  4788.7 2122.00
  4821.0 2121.67  4853.4 2123.12  4875.6 2122.06  4882.2 2120.66  4897.4 2121.27
  4911.1 2120.13  4934.4 2122.66  4963.3 2121.20  4986.7 2121.92  5004.0 2121.38
  5015.8 2118.84  5016.1 2118.34  5020.3 2118.84  5076.7 2127.01  5141.3 2133.80
  5264.0 2146.81  5272.4 2149.19  5286.3 2149.80  5294.7 2151.70  5331.1 2155.91
#Mann=6,-1,0
  4122.4    0.07       0  4128.7     0.1       0  4219.3    0.07       0
  5015.8    0.05       0  5020.3    0.07       0  5141.3     0.1       0
Bank Sta=5015.8,5020.3
Exp/Cntr=0.3,0.1

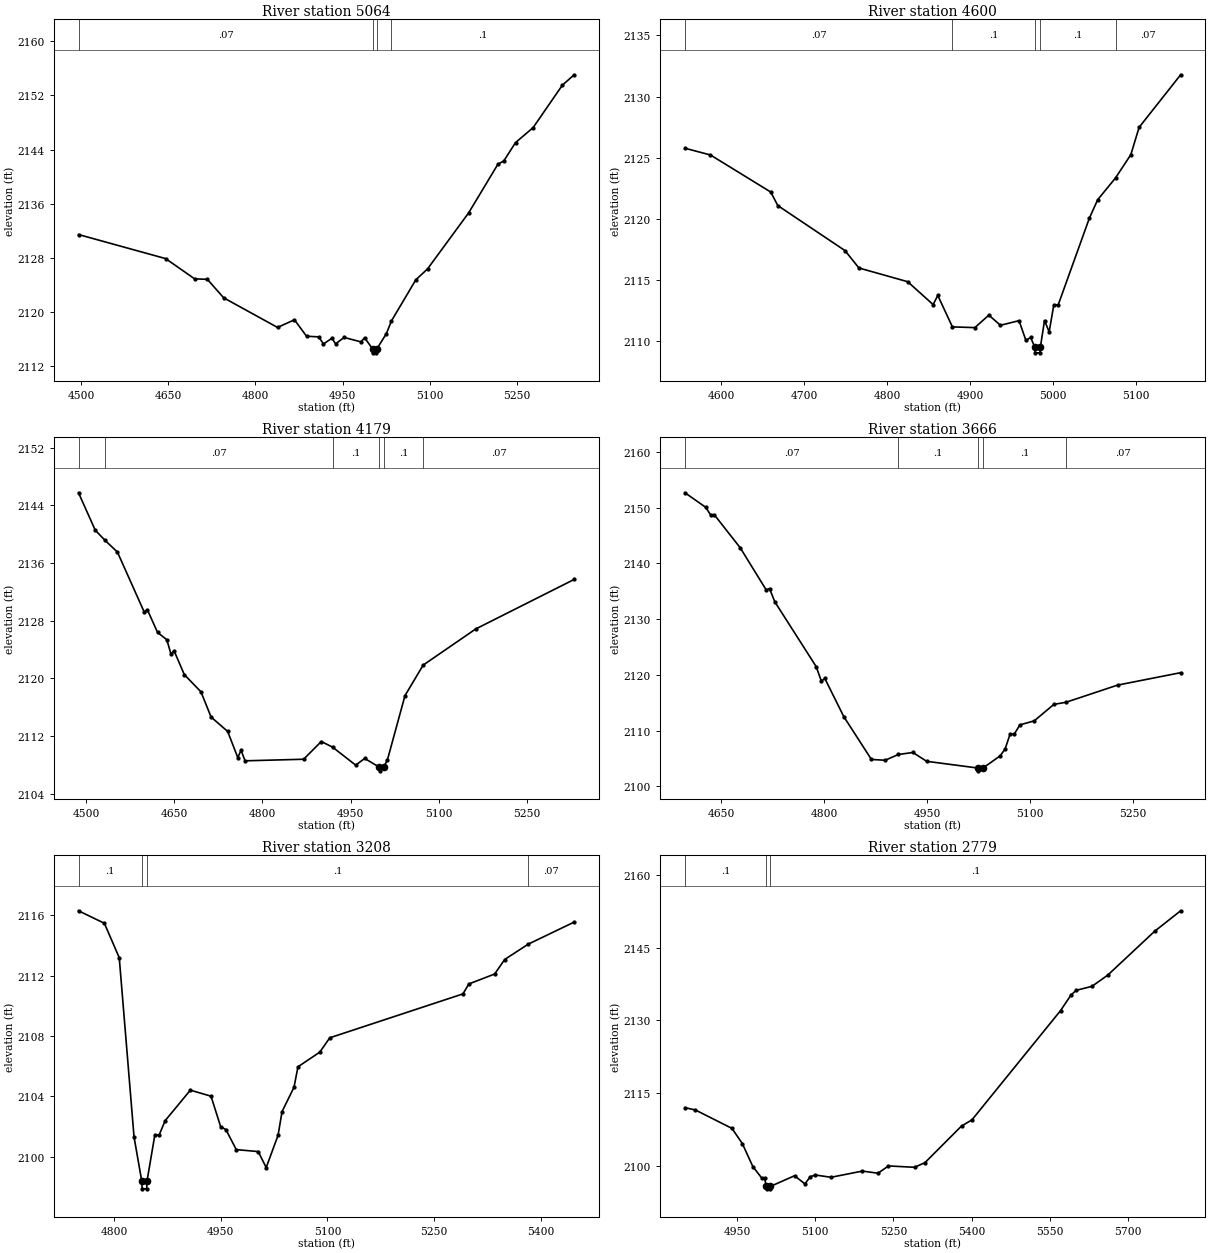
Type RM Length L Ch R = 1,5064,464,464,464
BEGIN DESCRIPTION:
Stream0104 11.0
END DESCRIPTION:
XS GIS Cut Line= 3
      1776574.98     13925475.03      1776875.00     13925075.00
      1776825.00     13924724.99
#Sta/Elev= 30
  4495.2 2131.46  4645.2 2127.91  4695.2 2124.92  4717.1 2124.85  4745.2 2122.12
  4837.9 2117.75  4867.1 2118.88  4887.9 2116.45  4908.8 2116.36  4917.1 2115.31
  4931.7 2116.16  4937.9 2115.32  4952.5 2116.27  4981.7 2115.62  4987.9 2116.23
  5002.3 2114.50  5002.8 2114.00  5007.9 2114.00  5008.4 2114.50  5025.5 2116.85
  5034.0 2118.69  5076.1 2124.78  5096.3 2126.39  5167.0 2134.65  5217.5 2141.84
  5227.6 2142.32  5247.8 2145.03  5278.1 2147.24  5328.6 2153.52  5348.8 2155.04
#Mann=4,-1,0
  4495.2    0.07       0  5002.3    0.05       0  5008.4    0.07       0
  5034.0     0.1       0
Bank Sta=5002.3,5008.4
Exp/Cntr=0.3,0.1

Type RM Length L Ch R = 1,4600,421,421,421
BEGIN DESCRIPTION:
Stream0104 10.0
END DESCRIPTION:
XS GIS Cut Line= 3
      1777075.02     13925374.96      1777275.00     13924975.00
      1777275.00     13924824.97
#Sta/Elev= 30
  4556.6 2125.78  4587.3 2125.23  4660.0 2122.20  4668.4 2121.10  4749.4 2117.42
  4766.2 2116.00  4824.9 2114.88  4855.6 2113.01  4861.2 2113.76  4878.8 2111.19
  4905.9 2111.13  4922.7 2112.15  4936.7 2111.32  4959.1 2111.70  4967.4 2110.08
  4973.0 2110.33  4977.9 2109.57  4978.4 2109.07  4984.4 2109.07  4984.9 2109.57
  4989.8 2111.71  4995.4 2110.78  5001.0 2112.99  5006.3 2112.99  5043.8 2120.06
  5053.8 2121.57  5075.4 2123.36  5093.8 2125.26  5103.8 2127.49  5153.8 2131.78
#Mann=5,-1,0
  4556.6    0.07       0  4878.8     0.1       0  4977.9    0.05       0
  4984.9     0.1       0  5075.4    0.07       0
Bank Sta=4977.9,4984.9
Exp/Cntr=0.3,0.1

Type RM Length L Ch R = 1,4179,513,513,513
BEGIN DESCRIPTION:
Stream0104 9.0
END DESCRIPTION:
XS GIS Cut Line= 3
      1777847.94     13925440.63      1777629.34     13924980.00
      1777609.57     13924648.06
#Sta/Elev= 30
  4487.4 2145.76  4515.8 2140.57  4532.3 2139.17  4553.5 2137.53  4599.0 2129.22
  4604.5 2129.51  4621.7 2126.38  4637.5 2125.36  4644.5 2123.38  4650.0 2123.79
  4667.2 2120.52  4695.5 2118.13  4712.7 2114.63  4740.9 2112.63  4758.1 2109.00
  4763.7 2110.03  4770.4 2108.55  4870.0 2108.77  4900.0 2111.23  4919.2 2110.45
  4958.5 2107.95  4973.8 2108.88  4998.8 2107.66  4999.3 2107.16  5005.8 2107.66
  5012.3 2108.65  5042.3 2117.61  5073.2 2121.84  5162.6 2126.86  5329.8 2133.73
#Mann=6,-1,0
  4487.4     0.1       0  4532.3    0.07       0  4919.2     0.1       0
  4998.8    0.05       0  5005.8     0.1       0  5073.2    0.07       0
Bank Sta=4998.8,5005.8
Exp/Cntr=0.3,0.1

Type RM Length L Ch R = 1,3666,458,458,458
BEGIN DESCRIPTION:
Stream0104 8.0
END DESCRIPTION:
XS GIS Cut Line= 3
      1778075.00     13925424.99      1778125.00     13925025.00
      1777924.97     13924774.97
#Sta/Elev= 30
  4596.9 2152.65  4627.1 2150.05  4634.7 2148.61  4639.7 2148.71  4677.5 2142.79
  4715.3 2135.26  4720.3 2135.47  4727.9 2133.12  4788.4 2121.47  4795.9 2118.88
  4801.0 2119.35  4828.7 2112.50  4869.0 2104.83  4889.1 2104.69  4908.2 2105.72
  4929.5 2106.08  4949.6 2104.50  5024.4 2103.29  5024.9 2102.79  5031.7 2103.29
  5056.8 2105.47  5064.0 2106.69  5071.2 2109.33  5077.6 2109.41  5085.6 2111.03
  5106.5 2111.75  5135.3 2114.71  5152.8 2115.08  5228.1 2118.16  5320.2 2120.39
#Mann=5,-1,0
  4596.9    0.07       0  4908.2     0.1       0  5024.4    0.05       0
  5031.7     0.1       0  5152.8    0.07       0
Bank Sta=5024.4,5031.7
Exp/Cntr=0.3,0.1

Type RM Length L Ch R = 1,3208,429,429,429
BEGIN DESCRIPTION:
Stream0104 7.0
END DESCRIPTION:
XS GIS Cut Line= 3
      1778724.99     13925024.99      1778525.00     13924875.00
      1778125.00     13924675.00
#Sta/Elev= 30
  4749.9 2116.29  4786.3 2115.46  4807.2 2113.18  4828.0 2101.30  4838.9 2098.36
  4839.4 2097.86  4845.7 2097.86  4846.2 2098.36  4857.2 2101.41  4863.4 2101.44
  4871.8 2102.38  4907.2 2104.40  4936.3 2104.00  4949.9 2101.97  4957.2 2101.79
  4971.8 2100.46  5002.7 2100.33  5013.9 2099.27  5030.6 2101.41  5036.2 2102.98
  5053.0 2104.59  5058.6 2105.95  5089.3 2106.92  5103.3 2107.87  5290.6 2110.78
  5299.0 2111.44  5335.3 2112.10  5349.3 2113.06  5382.6 2114.08  5447.1 2115.54
#Mann=4,-1,0
  4749.9     0.1       0  4838.9    0.05       0  4846.2     0.1       0
  5382.6    0.07       0
Bank Sta=4838.9,4846.2
Exp/Cntr=0.3,0.1

Type RM Length L Ch R = 1,2779,470,470,470
BEGIN DESCRIPTION:
Stream0104 6.0
END DESCRIPTION:
XS GIS Cut Line= 3
      1778875.00     13924875.00      1778875.00     13924725.00
      1778875.00     13923925.00
#Sta/Elev= 30
  4850.5 2112.01  4870.5 2111.53  4940.5 2107.74  4960.5 2104.60  4980.5 2099.88
  4998.0 2097.45  5003.0 2097.45  5006.7 2095.78  5007.2 2095.28  5013.7 2095.28
  5014.2 2095.78  5060.5 2097.98  5080.5 2096.29  5090.5 2097.78  5100.5 2098.13
  5130.5 2097.66  5190.5 2098.94  5220.5 2098.50  5240.5 2100.00  5290.5 2099.72
  5310.5 2100.68  5380.5 2108.22  5400.5 2109.49  5570.5 2132.03  5590.5 2135.24
  5600.5 2136.19  5630.5 2137.01  5660.5 2139.29  5750.5 2148.34  5800.5 2152.58
#Mann=3,-1,0
  4850.5     0.1       0  5006.7    0.05       0  5014.2     0.1       0
Bank Sta=5006.7,5014.2
Exp/Cntr=0.3,0.1

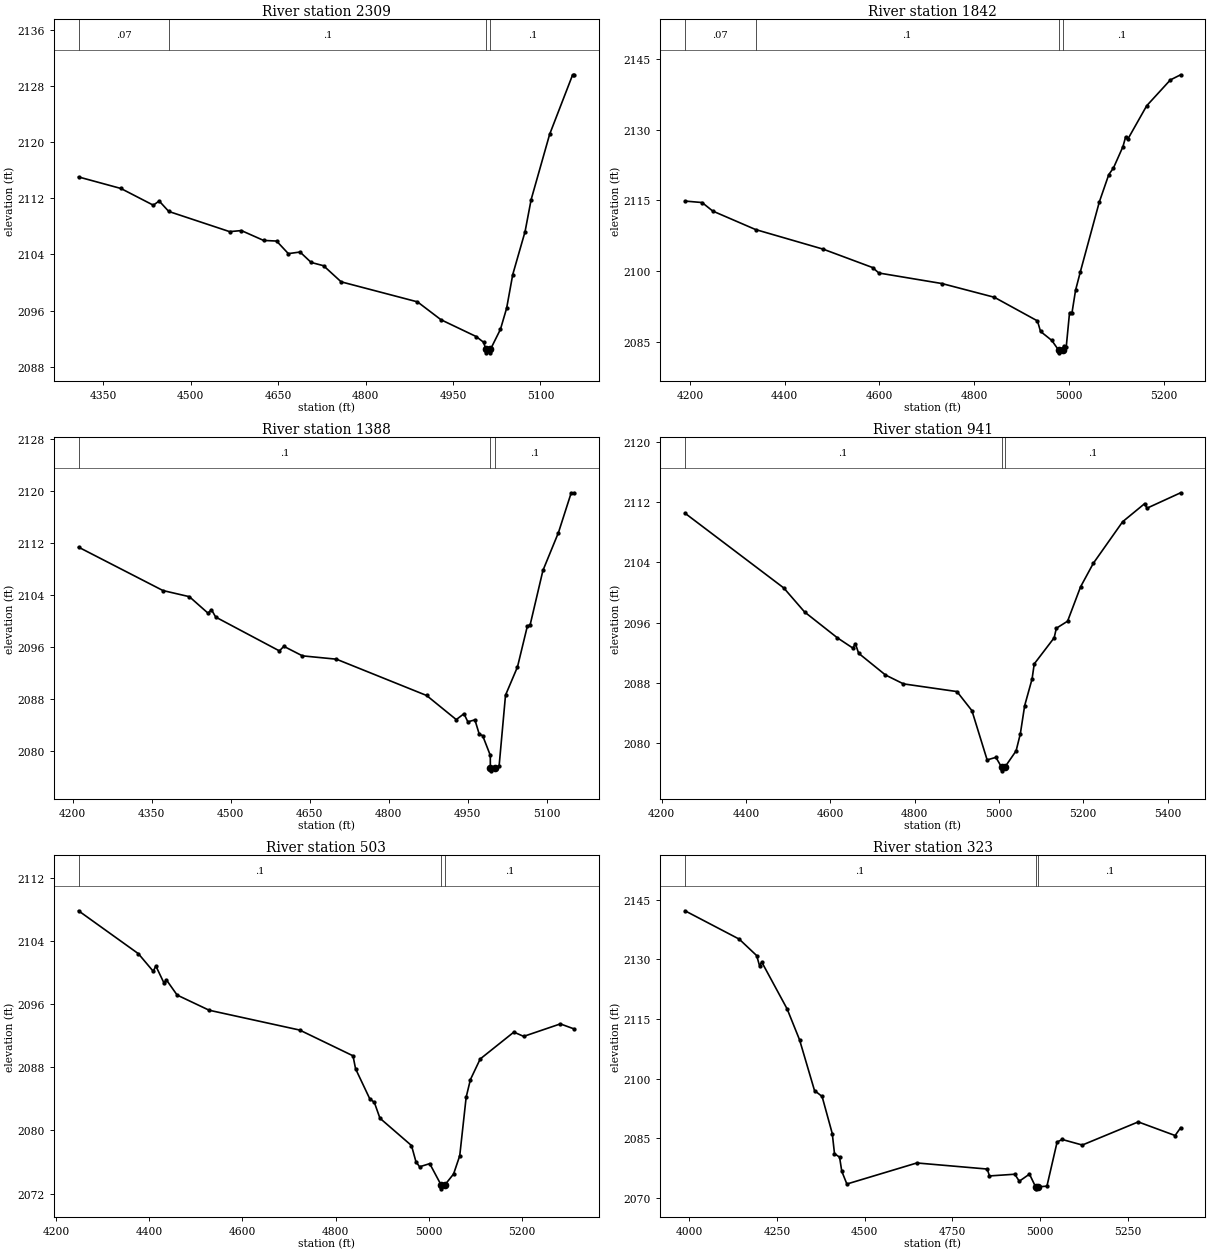
Type RM Length L Ch R = 1,2309,467,467,467
BEGIN DESCRIPTION:
Stream0104 5.0
END DESCRIPTION:
XS GIS Cut Line= 3
      1779258.76     13925062.42      1779175.00     13924375.00
      1779125.00     13924225.01
#Sta/Elev= 30
  4307.2 2115.03  4379.9 2113.39  4435.6 2111.01  4445.6 2111.61  4462.1 2110.12
  4566.5 2107.25  4586.7 2107.40  4624.8 2106.00  4647.1 2105.91  4667.3 2104.12
  4687.4 2104.35  4706.4 2102.87  4727.7 2102.40  4757.9 2100.11  4888.9 2097.26
  4929.2 2094.72  4989.6 2092.33  5002.3 2091.52  5006.3 2090.51  5006.8 2090.01
  5013.7 2090.01  5014.2 2090.51  5031.3 2093.36  5041.9 2096.36  5052.4 2101.15
  5073.5 2107.24  5084.0 2111.82  5115.7 2121.09  5155.2 2129.56  5157.8 2129.56
#Mann=4,-1,0
  4307.2    0.07       0  4462.1     0.1       0  5006.3    0.05       0
  5014.2     0.1       0
Bank Sta=5006.3,5014.2
Exp/Cntr=0.3,0.1

Type RM Length L Ch R = 1,1842,454,454,454
BEGIN DESCRIPTION:
Stream0104 4.0
END DESCRIPTION:
XS GIS Cut Line= 3
      1779340.98     13925088.81      1779625.00     13924325.00
      1779615.04     13924093.32
#Sta/Elev= 30
  4189.2 2114.83  4225.3 2114.52  4247.9 2112.71  4338.4 2108.79  4481.3 2104.63
  4585.4 2100.74  4598.7 2099.58  4731.8 2097.35  4842.5 2094.44  4933.6 2089.43
  4940.1 2087.20  4963.9 2085.29  4978.8 2083.16  4979.3 2082.66  4986.8 2083.16
  4988.9 2084.04  4994.3 2083.82  5001.4 2091.18  5006.6 2091.18  5014.1 2095.93
  5024.1 2099.80  5064.2 2114.62  5084.2 2120.43  5094.2 2121.86  5114.2 2126.38
  5119.9 2128.45  5124.9 2128.03  5164.3 2135.03  5214.3 2140.51  5236.0 2141.60
#Mann=4,-1,0
  4189.2    0.07       0  4338.4     0.1       0  4978.8    0.05       0
  4986.8     0.1       0
Bank Sta=4978.8,4986.8
Exp/Cntr=0.3,0.1

Type RM Length L Ch R = 1,1388,447,447,447
BEGIN DESCRIPTION:
Stream0104 3.0
END DESCRIPTION:
XS GIS Cut Line= 3
      1779553.25     13925107.34      1780025.00     13924475.00
      1780081.91     13924334.18
#Sta/Elev= 30
  4211.1 2111.35  4371.4 2104.69  4421.5 2103.75  4456.9 2101.22  4463.5 2101.75
  4471.5 2100.62  4592.4 2095.43  4600.8 2096.13  4636.2 2094.67  4700.6 2094.16
  4871.8 2088.59  4928.1 2084.89  4942.7 2085.79  4950.1 2084.55  4963.5 2084.85
  4971.9 2082.61  4978.1 2082.45  4992.7 2079.41  4992.8 2077.53  4993.3 2077.03
  5000.9 2077.53  5009.4 2077.74  5021.6 2088.64  5044.3 2092.97  5063.0 2099.22
  5068.4 2099.45  5092.6 2107.77  5122.1 2113.59  5146.2 2119.66  5151.9 2119.69
#Mann=3,-1,0
  4211.1     0.1       0  4992.8    0.05       0  5000.9     0.1       0
Bank Sta=4992.8,5000.9
Exp/Cntr=0.3,0.1

Type RM Length L Ch R = 1,941,438,438,438
BEGIN DESCRIPTION:
Stream0104 2.0
END DESCRIPTION:
XS GIS Cut Line= 3
      1779885.26     13925285.82      1780375.00     13924725.00
      1780454.86     13924301.52
#Sta/Elev= 30
  4255.4 2110.51  4489.7 2100.59  4539.1 2097.40  4616.9 2093.97  4653.0 2092.63
  4659.7 2093.16  4667.3 2091.92  4730.9 2089.04  4773.6 2087.86  4900.4 2086.84
  4935.9 2084.31  4972.0 2077.77  4992.8 2078.11  5006.1 2076.82  5006.6 2076.32
  5014.2 2076.82  5040.7 2078.97  5050.8 2081.25  5061.0 2084.97  5078.6 2088.52
  5083.7 2090.51  5131.0 2093.98  5136.1 2095.24  5162.8 2096.18  5193.6 2100.74
  5223.8 2103.86  5293.4 2109.38  5345.8 2111.79  5350.9 2111.17  5430.9 2113.22
#Mann=3,-1,0
  4255.4     0.1       0  5006.1    0.05       0  5014.2     0.1       0
Bank Sta=5006.1,5014.2
Exp/Cntr=0.3,0.1

Type RM Length L Ch R = 1,503,180,180,180
BEGIN DESCRIPTION:
Stream0104 1.0
END DESCRIPTION:
XS GIS Cut Line= 3
      1779998.53     13925339.41      1780675.00     13925025.00
      1780850.21     13924760.30
#Sta/Elev= 30
  4248.4 2107.81  4376.8 2102.38  4408.7 2100.15  4414.3 2100.82  4431.6 2098.69
  4437.1 2099.05  4460.0 2097.14  4528.7 2095.22  4722.9 2092.71  4837.3 2089.45
  4842.8 2087.81  4873.1 2084.03  4883.1 2083.55  4895.1 2081.55  4962.8 2078.09
  4972.3 2076.05  4980.2 2075.40  5001.9 2075.80  5026.2 2073.11  5026.7 2072.61
  5034.4 2073.11  5053.1 2074.49  5066.3 2076.80  5080.1 2084.22  5089.2 2086.44
  5110.2 2089.05  5182.4 2092.45  5203.5 2091.91  5282.2 2093.49  5311.8 2092.85
#Mann=3,-1,0
  4248.4     0.1       0  5026.2    0.05       0  5034.4     0.1       0
Bank Sta=5026.2,5034.4
Exp/Cntr=0.3,0.1

Type RM Length L Ch R = 1,323,0,0,0
BEGIN DESCRIPTION:
Stream0104 0.0
END DESCRIPTION:
XS GIS Cut Line= 3
      1780198.30     13925916.07      1780887.93     13925031.10
      1780958.76     13924749.82
#Sta/Elev= 30
  3988.0 2142.17  4142.5 2135.05  4192.3 2130.91  4200.4 2128.35  4206.7 2129.29
  4279.1 2117.50  4314.4 2109.76  4357.0 2097.02  4378.6 2095.53  4407.6 2086.21
  4413.9 2081.18  4428.4 2080.28  4434.7 2076.74  4449.2 2073.54  4648.6 2078.83
  4849.1 2077.30  4855.4 2075.57  4927.5 2076.00  4940.4 2074.24  4969.4 2076.03
  4986.8 2072.83  4987.3 2072.33  4995.0 2072.83  5019.1 2073.01  5048.1 2084.09
  5062.6 2084.73  5119.9 2083.33  5279.2 2089.14  5384.3 2085.72  5400.0 2087.69
#Mann=3,-1,0
  3988.0     0.1       0  4986.8    0.05       0  4995.0     0.1       0
Bank Sta=4986.8,4995
Exp/Cntr=0.3,0.1

Chan Stop Cuts=-1