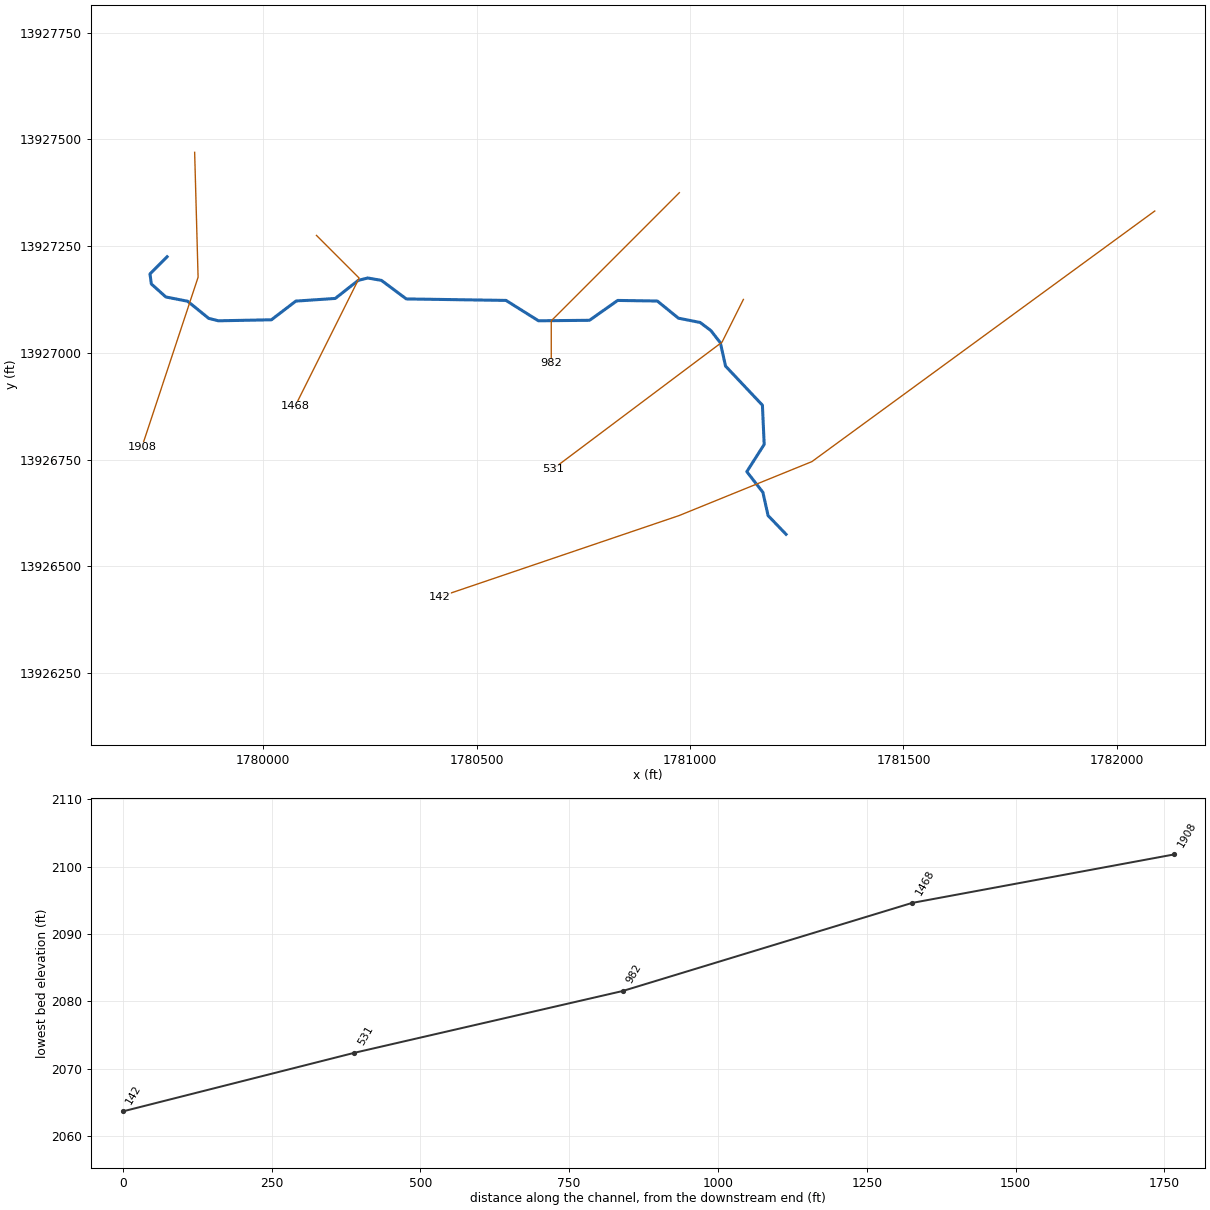
--- Stream0105.prj (project) ---

Proj Title=Stream0105 Base Level Engineering
Current Plan=p01
Default Exp/Contr=0.3,0.1
English Units
Geom File=g01
Flow File=f01
Plan File=p01
BEGIN DESCRIPTION:
Stream0105
END DESCRIPTION:

--- Stream0105.p01 (plan) ---

Plan Title=Multiple Run
Short Identifier=Multiple
Geom File=g01
Flow File=f01
Subcritical Flow
K Sum by GR= 0
Std Step Tol= 0.01
Critical Tol= 0.01
Num of Std Step Trials= 20
Max Error Tol= 0.3
Flow Tol Ratio= 0.001
Split Flow NTrial= 30
Split Flow Tol= 0.02
Split Flow Ratio= 0.02
Log Output Level= 0
Friction Slope Method= 1
Unsteady Friction Slope Method= 2
Unsteady Bridges Friction Slope Method= 1
Parabolic Critical Depth
Global Vel Dist=  1 , 1 , 1
Global Log Level= 0
CheckData=True
Encroach Param= -1, 0, 0, 0
BEGIN DESCRIPTION:
Multiple Run
END DESCRIPTION:

--- Stream0105.f01 (steady flow) ---

Flow Title=Multiple
Number of Profiles=7
Profile Names=10-year,25-year,50-year,1pct_min,100-year,1pct_plu,500-year
River Rch & RM= Stream0105,Reach-1,1908
    1018    1753    2458    1667    3327    6637    6024
Boundary for River Rch & Prof#=Stream0105,Reach-1,1
Up Type=0
Dn Type=3
Dn Slope=0.005
Boundary for River Rch & Prof#=Stream0105,Reach-1,2
Up Type=0
Dn Type=3
Dn Slope=0.005
Boundary for River Rch & Prof#=Stream0105,Reach-1,3
Up Type=0
Dn Type=3
Dn Slope=0.005
Boundary for River Rch & Prof#=Stream0105,Reach-1,4
Up Type=0
Dn Type=3
Dn Slope=0.005
Boundary for River Rch & Prof#=Stream0105,Reach-1,5
Up Type=0
Dn Type=3
Dn Slope=0.005
Boundary for River Rch & Prof#=Stream0105,Reach-1,6
Up Type=0
Dn Type=3
Dn Slope=0.005
Boundary for River Rch & Prof#=Stream0105,Reach-1,7
Up Type=0
Dn Type=3
Dn Slope=0.005

--- Stream0105.g01 (geometry) ---

Geom Title=Existing Conditions

River Reach=Stream0105,Reach-1
Reach XY= 30
      1779775.00     13927225.00      1779735.02     13927184.81
      1779738.25     13927161.22      1779772.20     13927130.79
      1779823.20     13927120.79      1779872.65     13927080.70
      1779895.03     13927075.04      1780019.47     13927077.37
      1780076.60     13927121.14      1780169.03     13927127.38
      1780222.82     13927169.63      1780245.18     13927175.28
      1780277.18     13927169.62      1780335.50     13927126.24
      1780569.06     13927122.74      1780645.04     13927075.05
      1780764.49     13927076.21      1780830.57     13927122.71
      1780923.42     13927121.33      1780972.85     13927081.16
      1781023.58     13927071.14      1781048.84     13927052.15
      1781071.11     13927023.57      1781083.19     13926968.98
      1781169.59     13926877.42      1781173.74     13926785.49
      1781133.02     13926721.68      1781170.67     13926673.42
      1781182.88     13926618.86      1781225.00     13926575.00

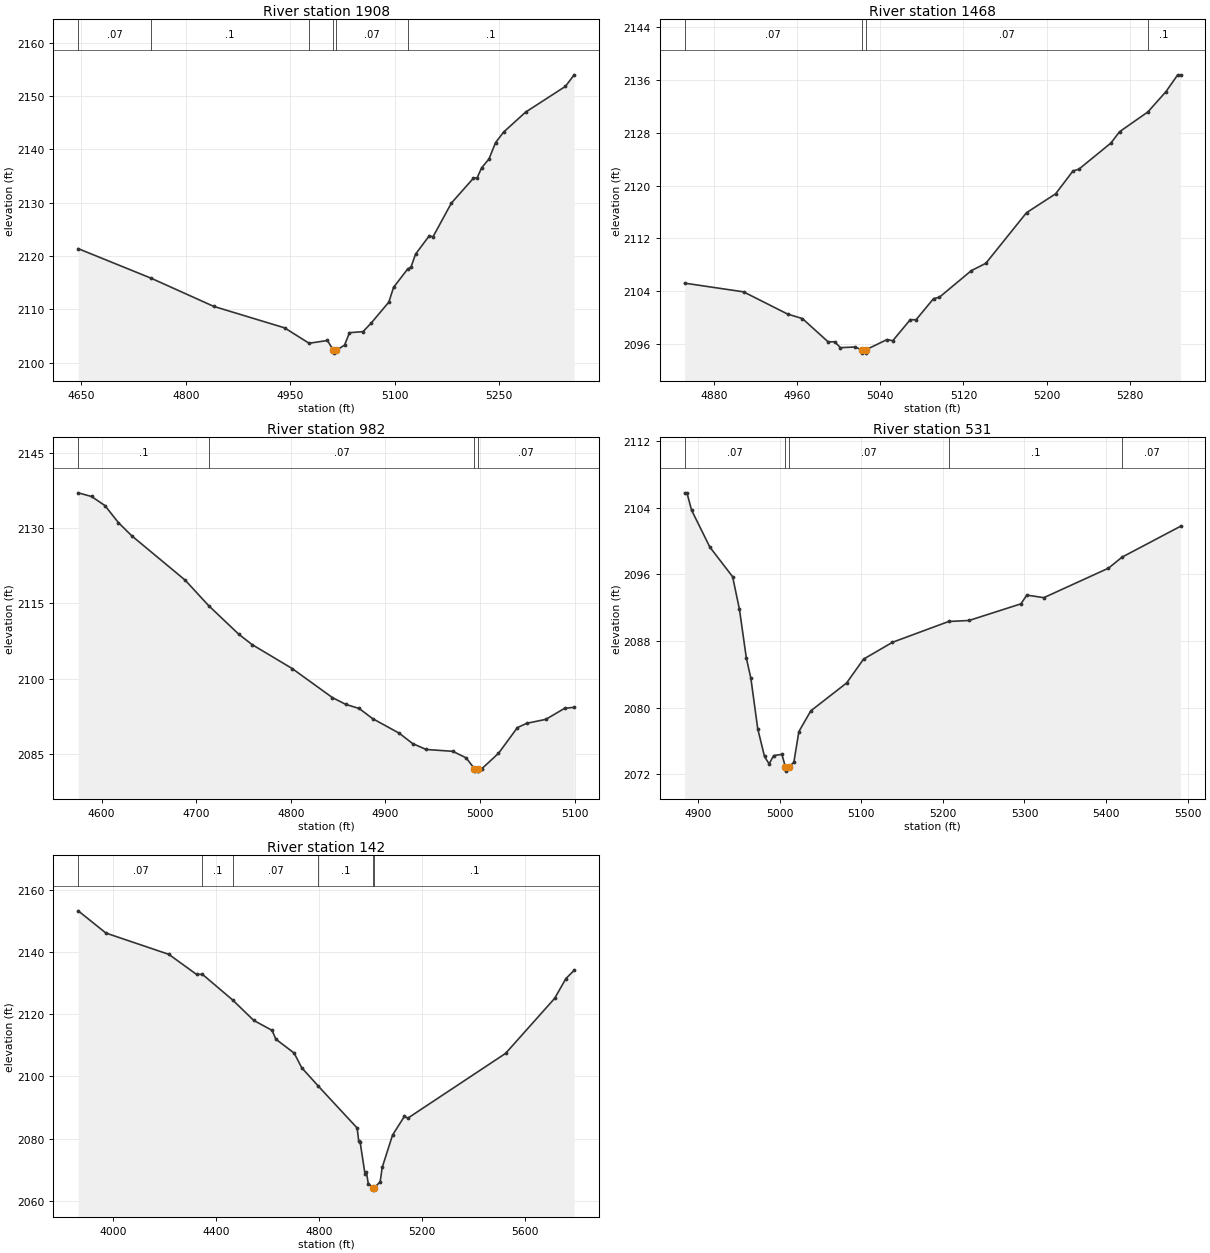
Type RM Length L Ch R = 1,1908,440,440,440
BEGIN DESCRIPTION:
Stream0105 4.0
END DESCRIPTION:
XS GIS Cut Line= 3
      1779839.64     13927469.53      1779847.70     13927177.02
      1779715.88     13926778.79
#Sta/Elev= 30
  4645.4 2121.38  4750.1 2115.84  4840.0 2110.56  4941.7 2106.54  4976.9 2103.65
  5003.3 2104.17  5011.9 2102.30  5012.1 2101.80  5015.9 2102.30  5027.9 2103.32
  5034.9 2105.63  5054.4 2105.83  5066.5 2107.50  5091.4 2111.36  5098.2 2114.13
  5118.7 2117.61  5123.1 2117.88  5129.8 2120.36  5149.5 2123.80  5154.8 2123.59
  5181.2 2129.92  5212.9 2134.59  5218.2 2134.66  5224.6 2136.53  5235.1 2138.16
  5244.6 2141.24  5256.2 2143.23  5287.8 2146.97  5345.0 2151.80  5357.5 2153.96
#Mann=6,-1,0
  4645.4    0.07       0  4750.1     0.1       0  4976.9    0.07       0
  5011.9    0.05       0  5015.9    0.07       0  5118.7     0.1       0
Bank Sta=5011.9,5015.9
Exp/Cntr=0.3,0.1

Type RM Length L Ch R = 1,1468,486,486,486
BEGIN DESCRIPTION:
Stream0105 3.0
END DESCRIPTION:
XS GIS Cut Line= 3
      1780124.98     13927275.02      1780225.00     13927175.00
      1780074.98     13926874.96
#Sta/Elev= 30
  4852.0 2105.22  4908.6 2103.90  4951.0 2100.53  4965.2 2099.85  4989.9 2096.33
  4996.2 2096.33  5001.8 2095.44  5015.8 2095.54  5022.2 2095.11  5022.4 2094.61
  5025.9 2094.61  5026.2 2095.11  5046.6 2096.67  5052.1 2096.49  5068.9 2099.68
  5074.5 2099.67  5091.3 2102.87  5096.9 2103.08  5127.6 2107.11  5141.6 2108.23
  5180.7 2115.90  5208.7 2118.76  5225.4 2122.23  5231.0 2122.49  5261.8 2126.45
  5270.2 2128.18  5297.4 2131.17  5314.9 2134.27  5326.1 2136.80  5328.9 2136.80
#Mann=4,-1,0
  4852.0    0.07       0  5022.2    0.05       0  5026.2    0.07       0
  5297.4     0.1       0
Bank Sta=5022.2,5026.2
Exp/Cntr=0.3,0.1

Type RM Length L Ch R = 1,982,451,451,451
BEGIN DESCRIPTION:
Stream0105 2.0
END DESCRIPTION:
XS GIS Cut Line= 3
      1780974.98     13927374.98      1780675.00     13927075.00
      1780675.00     13926975.03
#Sta/Elev= 30
  4575.3 2137.04  4589.4 2136.31  4603.6 2134.49  4617.7 2131.12  4631.8 2128.49
  4688.4 2119.62  4713.1 2114.56  4745.0 2108.85  4759.1 2106.78  4801.5 2102.00
  4844.0 2096.21  4858.1 2094.86  4872.3 2094.04  4886.4 2092.03  4914.7 2089.10
  4928.8 2087.04  4943.0 2085.87  4971.2 2085.50  4985.4 2084.19  4994.0 2082.05
  4994.2 2081.55  4997.7 2081.55  4998.0 2082.05  5002.0 2082.05  5019.5 2085.09
  5039.5 2090.23  5049.5 2091.09  5069.5 2091.87  5089.5 2094.08  5099.5 2094.27
#Mann=4,-1,0
  4575.3     0.1       0  4713.1    0.07       0  4994.0    0.05       0
  4998.0    0.07       0
Bank Sta=4994,4998
Exp/Cntr=0.3,0.1

Type RM Length L Ch R = 1,531,389,389,389
BEGIN DESCRIPTION:
Stream0105 1.0
END DESCRIPTION:
XS GIS Cut Line= 3
      1781125.01     13927125.02      1781075.00     13927025.00
      1780678.51     13926727.53
#Sta/Elev= 30
  4883.8 2105.80  4886.6 2105.80  4892.2 2103.73  4914.6 2099.29  4942.5 2095.73
  4950.9 2091.81  4959.3 2085.98  4964.9 2083.52  4973.3 2077.46  4981.6 2074.14
  4987.2 2073.25  4992.8 2074.25  5002.9 2074.39  5007.2 2072.88  5007.4 2072.38
  5011.2 2072.88  5017.5 2073.43  5023.7 2077.13  5038.3 2079.62  5082.1 2082.96
  5102.9 2085.83  5138.3 2087.85  5207.2 2090.35  5232.1 2090.47  5295.7 2092.47
  5302.9 2093.52  5323.7 2093.21  5402.9 2096.75  5419.6 2098.08  5491.3 2101.79
#Mann=5,-1,0
  4883.8    0.07       0  5007.2    0.05       0  5011.2    0.07       0
  5207.2     0.1       0  5419.6    0.07       0
Bank Sta=5007.2,5011.2
Exp/Cntr=0.3,0.1

Type RM Length L Ch R = 1,142,0,0,0
BEGIN DESCRIPTION:
Stream0105 0.0
END DESCRIPTION:
XS GIS Cut Line= 4
      1782088.65     13927332.14      1781285.53     13926745.28
      1780974.11     13926618.78      1780413.33     13926428.52
#Sta/Elev= 30
  3865.9 2153.36  3973.5 2146.19  4217.2 2139.34  4324.8 2132.87  4347.5 2132.90
  4464.7 2124.64  4546.5 2118.05  4617.5 2114.85  4632.2 2112.01  4703.2 2107.53
  4732.6 2102.80  4797.1 2096.86  4947.5 2083.38  4953.6 2079.15  4959.0 2078.88
  4977.7 2068.68  4983.1 2069.29  4990.7 2065.42  5010.6 2064.19  5010.8 2063.69
  5014.6 2064.19  5036.7 2066.04  5044.7 2070.70  5084.8 2081.13  5131.0 2087.17
  5143.8 2086.55  5523.1 2107.43  5713.2 2125.15  5757.0 2131.53  5788.9 2134.20
#Mann=6,-1,0
  3865.9    0.07       0  4347.5     0.1       0  4464.7    0.07       0
  4797.1     0.1       0  5010.6    0.05       0  5014.6     0.1       0
Bank Sta=5010.6,5014.6
Exp/Cntr=0.3,0.1

Chan Stop Cuts=-1