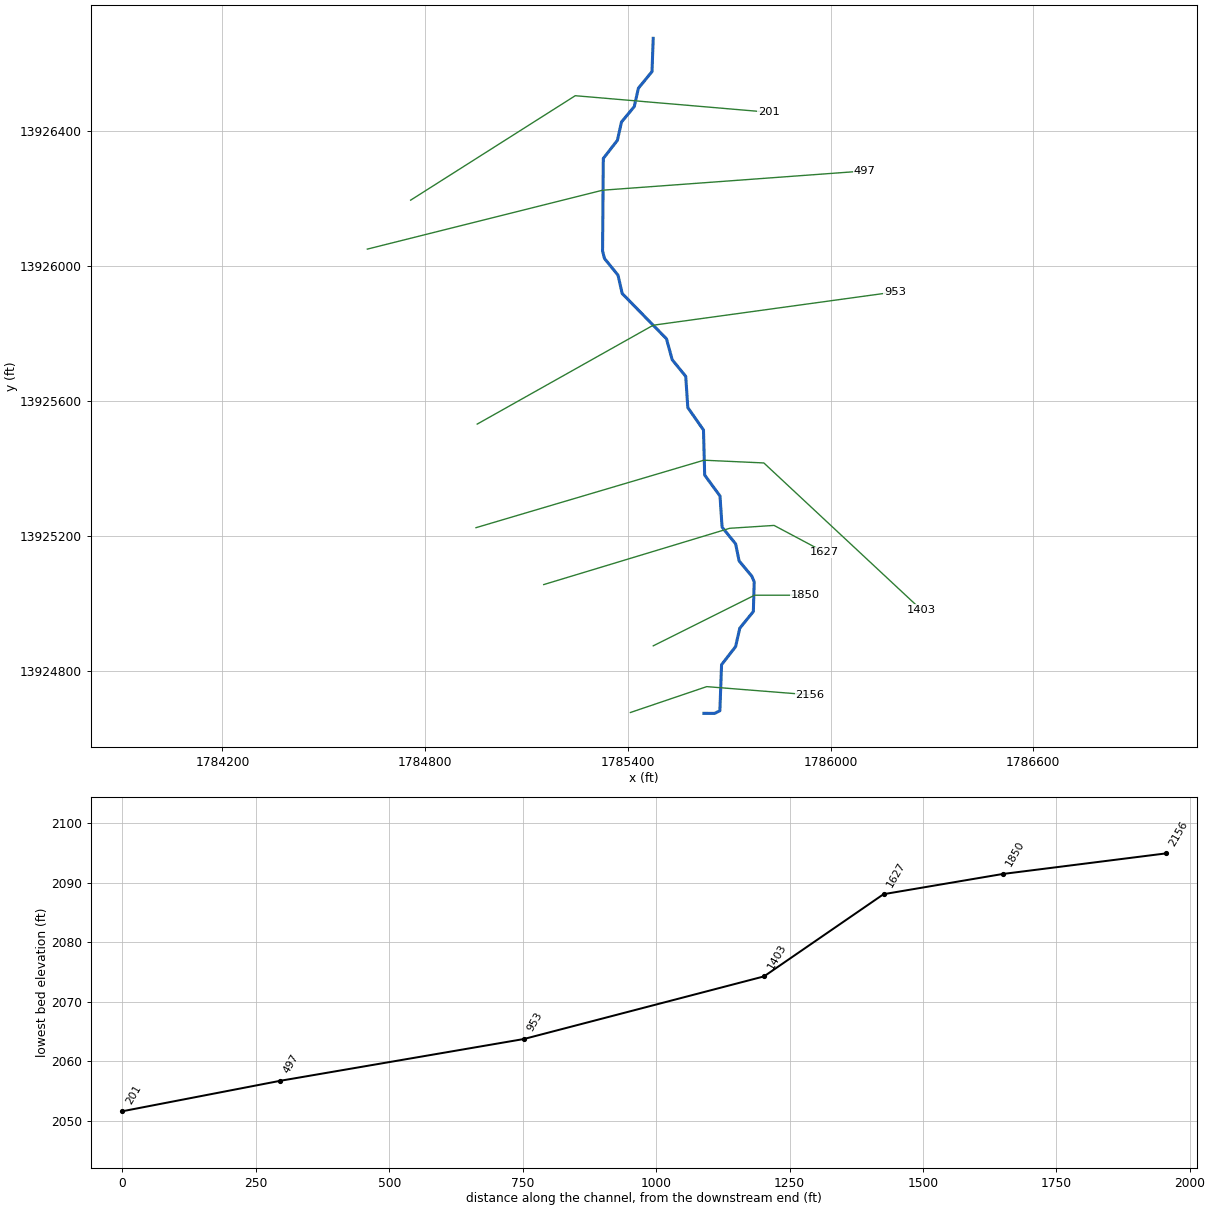
--- Stream0106.prj (project) ---

Proj Title=Stream0106 Base Level Engineering
Current Plan=p01
Default Exp/Contr=0.3,0.1
English Units
Geom File=g01
Flow File=f01
Plan File=p01
BEGIN DESCRIPTION:
Stream0106
END DESCRIPTION:

--- Stream0106.p01 (plan) ---

Plan Title=Multiple Run
Short Identifier=Multiple
Geom File=g01
Flow File=f01
Subcritical Flow
K Sum by GR= 0
Std Step Tol= 0.01
Critical Tol= 0.01
Num of Std Step Trials= 20
Max Error Tol= 0.3
Flow Tol Ratio= 0.001
Split Flow NTrial= 30
Split Flow Tol= 0.02
Split Flow Ratio= 0.02
Log Output Level= 0
Friction Slope Method= 1
Unsteady Friction Slope Method= 2
Unsteady Bridges Friction Slope Method= 1
Parabolic Critical Depth
Global Vel Dist=  1 , 1 , 1
Global Log Level= 0
CheckData=True
Encroach Param= -1, 0, 0, 0
BEGIN DESCRIPTION:
Multiple Run
END DESCRIPTION:

--- Stream0106.f01 (steady flow) ---

Flow Title=Multiple
Number of Profiles=7
Profile Names=10-year,25-year,50-year,1pct_min,100-year,1pct_plu,500-year
River Rch & RM= Stream0106,Reach-1,2156
    1046    1801    2525    1712    3415    6814    6175
Boundary for River Rch & Prof#=Stream0106,Reach-1,1
Up Type=0
Dn Type=3
Dn Slope=0.005
Boundary for River Rch & Prof#=Stream0106,Reach-1,2
Up Type=0
Dn Type=3
Dn Slope=0.005
Boundary for River Rch & Prof#=Stream0106,Reach-1,3
Up Type=0
Dn Type=3
Dn Slope=0.005
Boundary for River Rch & Prof#=Stream0106,Reach-1,4
Up Type=0
Dn Type=3
Dn Slope=0.005
Boundary for River Rch & Prof#=Stream0106,Reach-1,5
Up Type=0
Dn Type=3
Dn Slope=0.005
Boundary for River Rch & Prof#=Stream0106,Reach-1,6
Up Type=0
Dn Type=3
Dn Slope=0.005
Boundary for River Rch & Prof#=Stream0106,Reach-1,7
Up Type=0
Dn Type=3
Dn Slope=0.005

--- Stream0106.g01 (geometry) ---

Geom Title=Existing Conditions

River Reach=Stream0106,Reach-1
Reach XY= 30
      1785625.00     13924675.00      1785656.95     13924674.90
      1785672.28     13924682.71      1785677.24     13924819.07
      1785718.88     13924872.82      1785731.12     13924927.18
      1785771.33     13924976.58      1785773.92     13925064.46
      1785766.96     13925081.05      1785729.19     13925126.73
      1785718.89     13925177.18      1785678.83     13925226.58
      1785672.64     13925319.02      1785627.27     13925380.94
      1785623.77     13925514.49      1785577.36     13925580.98
      1785571.18     13925673.42      1785531.14     13925722.83
      1785514.24     13925784.68      1785383.14     13925918.94
      1785370.78     13925973.25      1785330.71     13926022.65
      1785325.06     13926045.03      1785327.24     13926319.07
      1785368.88     13926372.82      1785381.08     13926427.20
      1785418.92     13926472.80      1785431.09     13926527.19
      1785471.37     13926576.50      1785475.00     13926675.00

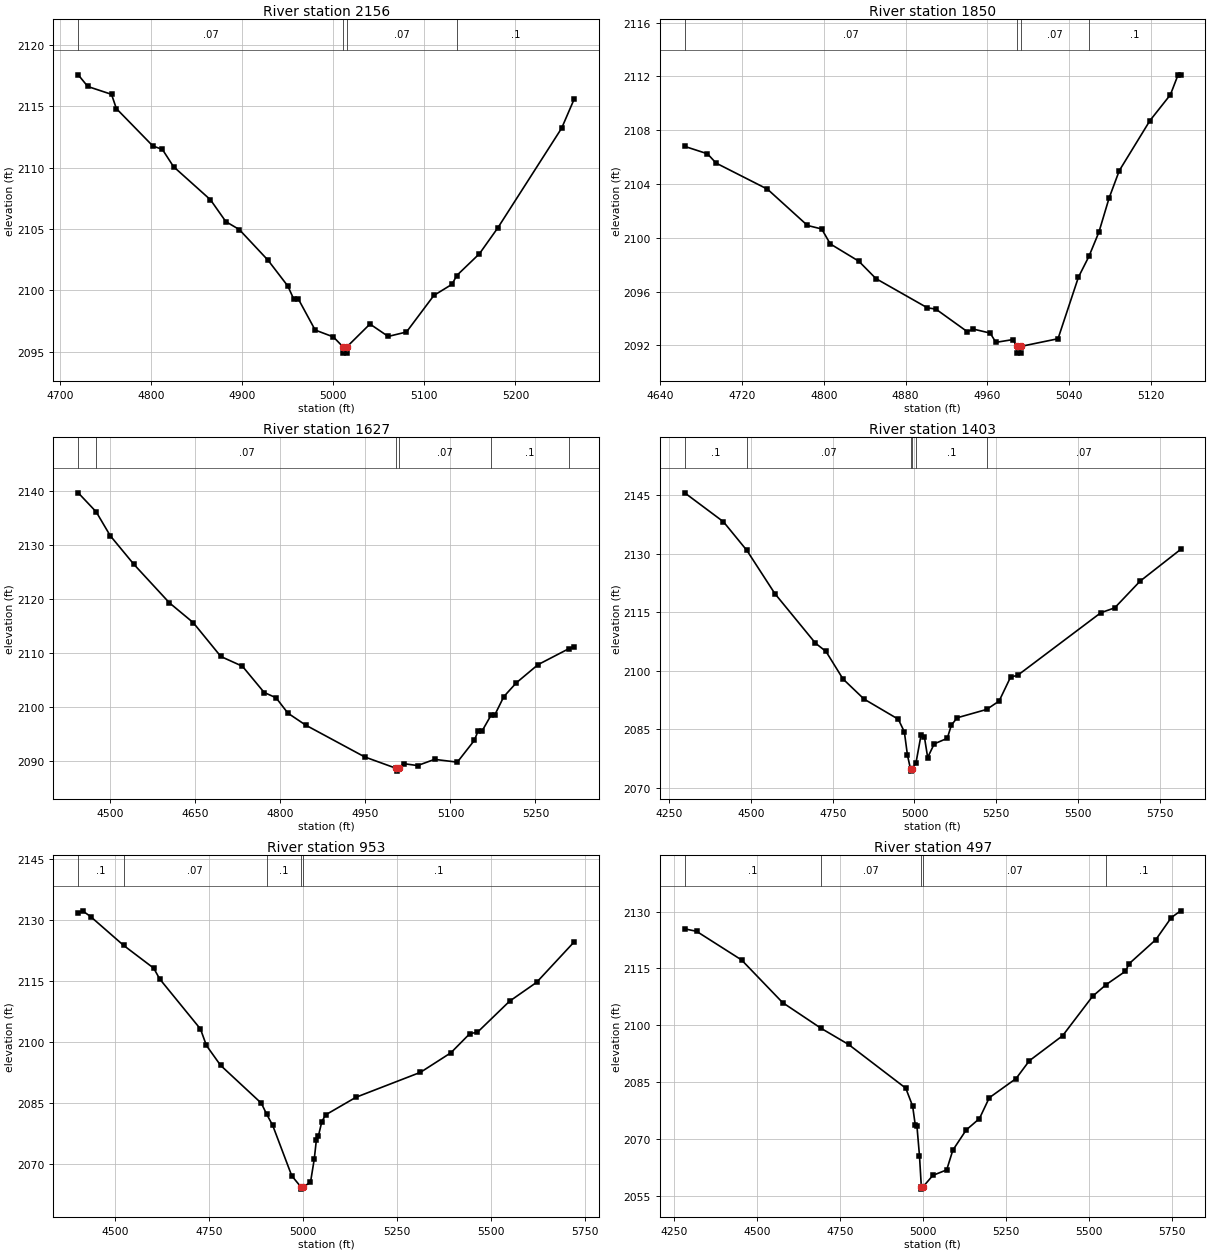
Type RM Length L Ch R = 1,2156,306,306,306
BEGIN DESCRIPTION:
Stream0106 5.0
END DESCRIPTION:
XS GIS Cut Line= 3
      1785407.45     13924677.51      1785633.28     13924754.13
      1785938.64     13924729.88
#Sta/Elev= 30
  4719.7 2117.56  4730.2 2116.61  4756.3 2115.97  4761.6 2114.81  4801.6 2111.77
  4812.2 2111.48  4824.4 2110.08  4865.0 2107.38  4881.9 2105.60  4896.6 2104.96
  4928.3 2102.45  4950.0 2100.35  4956.4 2099.30  4961.5 2099.30  4980.0 2096.77
  5000.0 2096.21  5010.7 2095.39  5011.0 2094.89  5014.5 2094.89  5014.7 2095.39
  5040.2 2097.26  5060.2 2096.25  5080.3 2096.61  5110.4 2099.59  5130.4 2100.50
  5135.5 2101.21  5160.5 2102.99  5180.6 2105.09  5250.8 2113.22  5264.5 2115.58
#Mann=4,-1,0
  4719.7    0.07       0  5010.7    0.05       0  5014.7    0.07       0
  5135.5     0.1       0
Bank Sta=5010.7,5014.7
Exp/Cntr=0.3,0.1

Type RM Length L Ch R = 1,1850,223,223,223
BEGIN DESCRIPTION:
Stream0106 4.0
END DESCRIPTION:
XS GIS Cut Line= 3
      1785475.03     13924875.01      1785775.00     13925025.00
      1785925.02     13925025.00
#Sta/Elev= 30
  4663.8 2106.80  4686.1 2106.25  4694.5 2105.56  4744.8 2103.62  4784.0 2100.92
  4797.9 2100.66  4806.3 2099.55  4834.3 2098.26  4851.0 2096.97  4901.3 2094.80
  4909.7 2094.70  4940.5 2093.02  4946.1 2093.22  4962.8 2092.92  4968.4 2092.23
  4985.2 2092.44  4988.8 2091.93  4989.0 2091.43  4992.5 2091.43  4992.8 2091.93
  5029.2 2092.50  5049.2 2097.08  5059.5 2098.63  5069.2 2100.42  5079.2 2102.96
  5089.2 2105.00  5119.2 2108.72  5139.2 2110.64  5146.7 2112.12  5149.2 2112.12
#Mann=4,-1,0
  4663.8    0.07       0  4988.8    0.05       0  4992.8    0.07       0
  5059.5     0.1       0
Bank Sta=4988.8,4992.8
Exp/Cntr=0.3,0.1

Type RM Length L Ch R = 1,1627,224,224,224
BEGIN DESCRIPTION:
Stream0106 3.1
END DESCRIPTION:
XS GIS Cut Line= 4
      1785150.89     13925056.50      1785701.40     13925223.29
      1785832.69     13925231.79      1785981.36     13925152.66
#Sta/Elev= 30
  4443.1 2139.58  4474.8 2136.06  4499.6 2131.64  4541.4 2126.33  4604.1 2119.20
  4645.9 2115.56  4694.8 2109.27  4732.9 2107.46  4771.3 2102.60  4792.2 2101.63
  4813.1 2098.78  4844.4 2096.57  4948.9 2090.66  5004.7 2088.54  5004.9 2088.04
  5008.7 2088.54  5017.6 2089.42  5042.0 2089.07  5072.0 2090.22  5112.1 2089.70
  5142.2 2093.74  5148.5 2095.42  5155.9 2095.49  5172.1 2098.48  5177.9 2098.38
  5194.2 2101.84  5216.2 2104.39  5254.4 2107.75  5309.4 2110.74  5318.3 2111.09
#Mann=6,-1,0
  4443.1     0.1       0  4474.8    0.07       0  5004.7    0.05       0
  5008.7    0.07       0  5172.1     0.1       0  5309.4    0.07       0
Bank Sta=5004.7,5008.7
Exp/Cntr=0.3,0.1

Type RM Length L Ch R = 1,1403,450,450,450
BEGIN DESCRIPTION:
Stream0106 3.0
END DESCRIPTION:
XS GIS Cut Line= 4
      1784950.37     13925225.10      1785625.00     13925425.00
      1785802.46     13925416.90      1786267.69     13924982.46
#Sta/Elev= 30
  4296.7 2145.61  4415.3 2138.19  4487.1 2130.83  4572.7 2119.76  4696.9 2107.05
  4729.2 2104.92  4781.3 2097.86  4845.5 2092.72  4950.5 2087.54  4969.0 2084.30
  4978.5 2078.32  4987.9 2074.73  4988.1 2074.23  4991.9 2074.73  5004.5 2076.31
  5020.3 2083.58  5030.4 2082.98  5040.4 2077.72  5060.4 2081.22  5100.4 2082.65
  5112.7 2085.99  5130.5 2087.91  5220.8 2090.05  5259.0 2092.20  5294.2 2098.37
  5315.7 2098.80  5570.2 2114.85  5612.7 2116.10  5690.4 2122.95  5814.5 2131.09
#Mann=6,-1,0
  4296.7     0.1       0  4487.1    0.07       0  4987.9    0.05       0
  4991.9    0.07       0  5004.5     0.1       0  5220.8    0.07       0
Bank Sta=4987.9,4991.9
Exp/Cntr=0.3,0.1

Type RM Length L Ch R = 1,953,456,456,456
BEGIN DESCRIPTION:
Stream0106 2.0
END DESCRIPTION:
XS GIS Cut Line= 3
      1784954.00     13925532.04      1785475.00     13925825.00
      1786189.93     13925923.53
#Sta/Elev= 30
  4402.0 2131.70  4413.6 2132.20  4435.2 2130.77  4522.7 2123.70  4602.9 2118.08
  4618.8 2115.43  4727.2 2103.12  4743.1 2099.06  4780.7 2094.18  4889.1 2084.86
  4903.3 2082.16  4919.4 2079.40  4970.1 2066.99  4994.8 2064.21  4995.1 2063.71
  4998.8 2064.21  5019.9 2065.35  5030.0 2071.10  5035.7 2075.92  5040.7 2076.67
  5050.2 2080.35  5060.3 2081.99  5141.0 2086.32  5312.6 2092.46  5393.4 2097.26
  5443.9 2101.98  5464.1 2102.31  5549.5 2109.95  5621.4 2114.59  5721.4 2124.55
#Mann=5,-1,0
  4402.0     0.1       0  4522.7    0.07       0  4903.3     0.1       0
  4994.8    0.05       0  4998.8     0.1       0
Bank Sta=4994.8,4998.8
Exp/Cntr=0.3,0.1

Type RM Length L Ch R = 1,497,296,296,296
BEGIN DESCRIPTION:
Stream0106 1.0
END DESCRIPTION:
XS GIS Cut Line= 3
      1784628.75     13926050.47      1785325.00     13926225.00
      1786099.52     13926281.96
#Sta/Elev= 30
  4282.3 2125.47  4318.0 2124.82  4453.7 2117.25  4577.4 2105.98  4693.3 2099.19
  4776.2 2094.92  4948.5 2083.37  4969.2 2078.64  4976.9 2073.76  4982.1 2073.43
  4989.8 2065.54  4995.5 2057.20  4995.8 2056.70  4999.5 2057.20  5030.2 2060.34
  5071.8 2061.78  5090.3 2066.99  5130.4 2072.31  5170.5 2075.34  5200.1 2080.84
  5280.8 2085.91  5321.0 2090.63  5421.2 2097.24  5511.5 2107.65  5552.4 2110.74
  5610.2 2114.25  5621.8 2116.28  5702.0 2122.62  5748.6 2128.44  5776.7 2130.23
#Mann=5,-1,0
  4282.3     0.1       0  4693.3    0.07       0  4995.5    0.05       0
  4999.5    0.07       0  5552.4     0.1       0
Bank Sta=4995.5,4999.5
Exp/Cntr=0.3,0.1

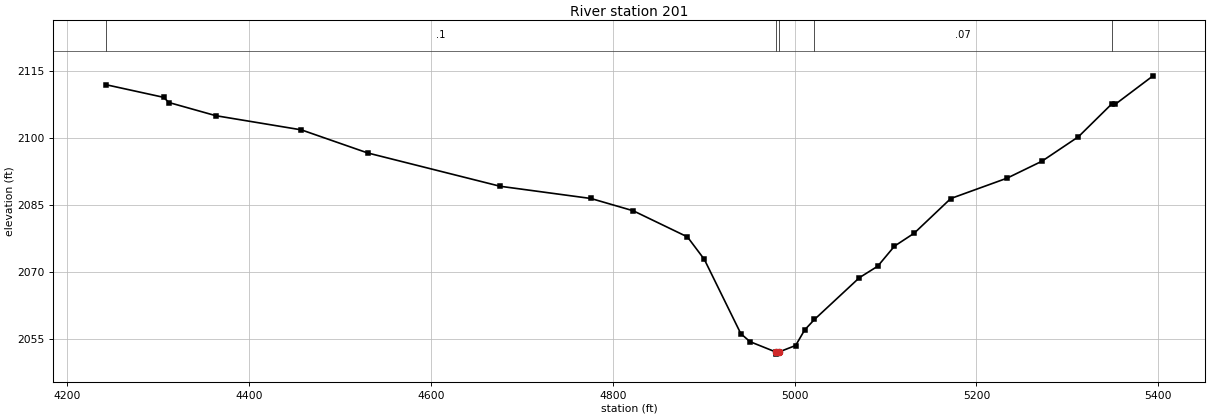
Type RM Length L Ch R = 1,201,0,0,0
BEGIN DESCRIPTION:
Stream0106 0.0
END DESCRIPTION:
XS GIS Cut Line= 3
      1784756.98     13926195.55      1785244.24     13926505.02
      1785816.72     13926456.05
#Sta/Elev= 30
  4242.4 2111.92  4305.9 2109.09  4311.9 2107.92  4363.5 2104.97  4457.5 2101.80
  4530.4 2096.63  4676.1 2089.17  4776.0 2086.43  4822.5 2083.68  4882.1 2077.83
  4900.7 2072.79  4940.8 2056.17  4950.9 2054.37  4979.0 2052.08  4979.2 2051.58
  4983.0 2052.08  5001.1 2053.51  5011.1 2057.01  5021.8 2059.34  5071.3 2068.71
  5091.4 2071.27  5109.8 2075.76  5131.5 2078.66  5171.7 2086.42  5233.7 2090.99
  5272.0 2094.78  5312.2 2100.27  5348.6 2107.57  5352.6 2107.52  5394.2 2113.90
#Mann=5,-1,0
  4242.4     0.1       0  4979.0    0.05       0  4983.0     0.1       0
  5021.8    0.07       0  5348.6     0.1       0
Bank Sta=4979,4983
Exp/Cntr=0.3,0.1

Chan Stop Cuts=-1