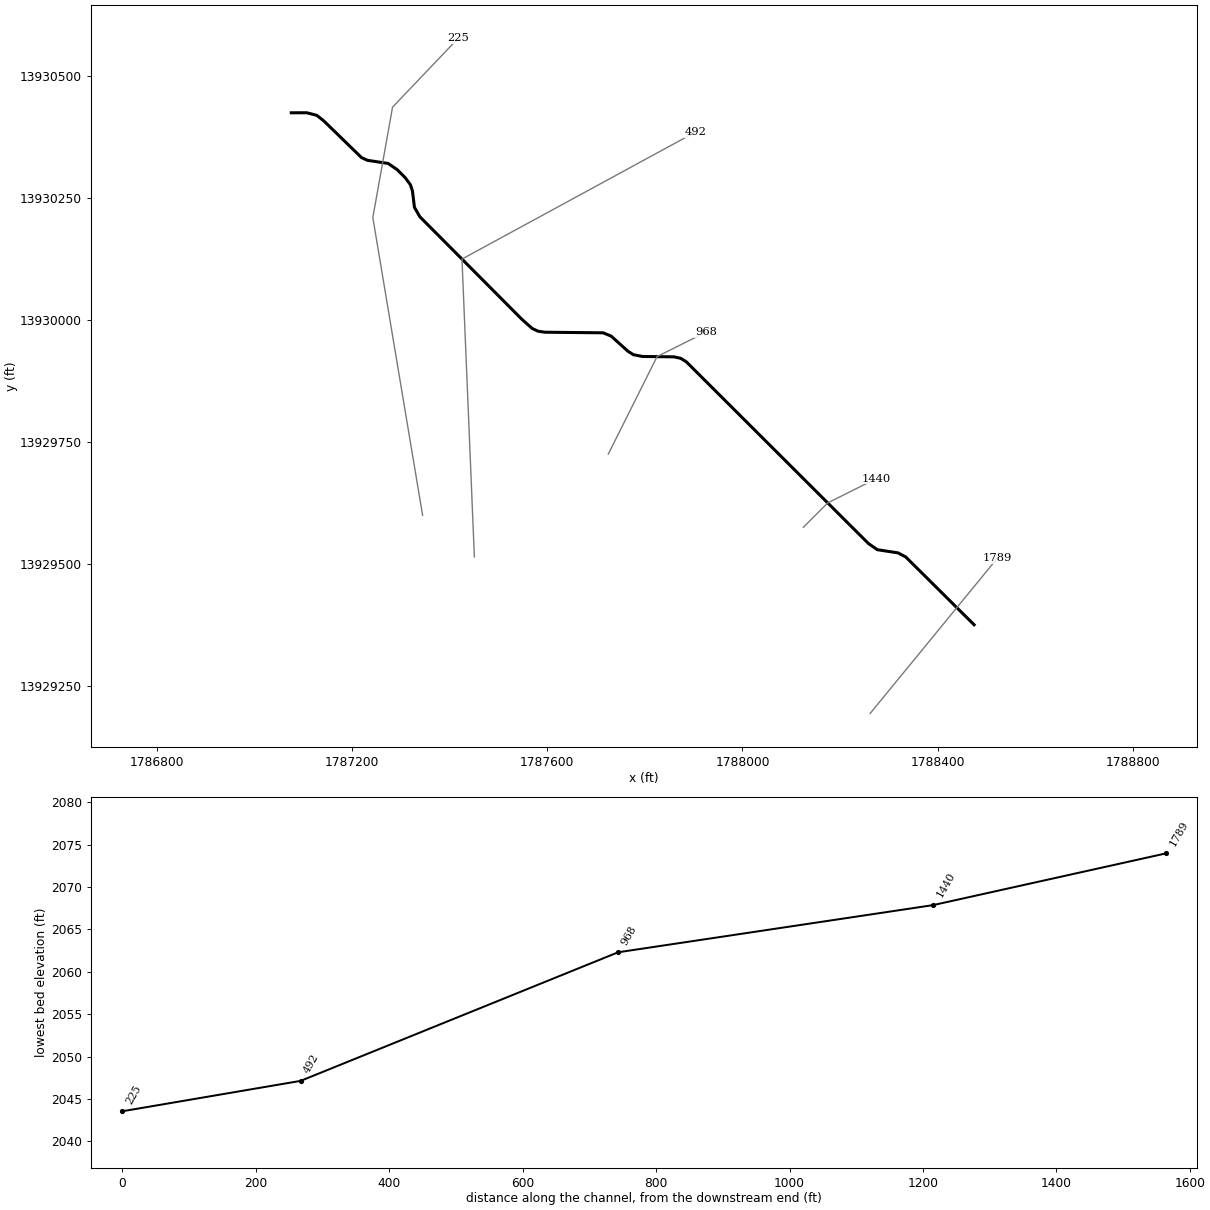
--- Stream0108.prj (project) ---

Proj Title=Stream0108 Base Level Engineering
Current Plan=p01
Default Exp/Contr=0.3,0.1
English Units
Geom File=g01
Flow File=f01
Plan File=p01
BEGIN DESCRIPTION:
Stream0108
END DESCRIPTION:

--- Stream0108.p01 (plan) ---

Plan Title=Multiple Run
Short Identifier=Multiple
Geom File=g01
Flow File=f01
Subcritical Flow
K Sum by GR= 0
Std Step Tol= 0.01
Critical Tol= 0.01
Num of Std Step Trials= 20
Max Error Tol= 0.3
Flow Tol Ratio= 0.001
Split Flow NTrial= 30
Split Flow Tol= 0.02
Split Flow Ratio= 0.02
Log Output Level= 0
Friction Slope Method= 1
Unsteady Friction Slope Method= 2
Unsteady Bridges Friction Slope Method= 1
Parabolic Critical Depth
Global Vel Dist=  1 , 1 , 1
Global Log Level= 0
CheckData=True
Encroach Param= -1, 0, 0, 0
BEGIN DESCRIPTION:
Multiple Run
END DESCRIPTION:

--- Stream0108.f01 (steady flow) ---

Flow Title=Multiple
Number of Profiles=7
Profile Names=10-year,25-year,50-year,1pct_min,100-year,1pct_plu,500-year
River Rch & RM= Stream0108,Reach-1,1789
     680    1141    1574    1052    2099    4187    3683
Boundary for River Rch & Prof#=Stream0108,Reach-1,1
Up Type=0
Dn Type=3
Dn Slope=0.005
Boundary for River Rch & Prof#=Stream0108,Reach-1,2
Up Type=0
Dn Type=3
Dn Slope=0.005
Boundary for River Rch & Prof#=Stream0108,Reach-1,3
Up Type=0
Dn Type=3
Dn Slope=0.005
Boundary for River Rch & Prof#=Stream0108,Reach-1,4
Up Type=0
Dn Type=3
Dn Slope=0.005
Boundary for River Rch & Prof#=Stream0108,Reach-1,5
Up Type=0
Dn Type=3
Dn Slope=0.005
Boundary for River Rch & Prof#=Stream0108,Reach-1,6
Up Type=0
Dn Type=3
Dn Slope=0.005
Boundary for River Rch & Prof#=Stream0108,Reach-1,7
Up Type=0
Dn Type=3
Dn Slope=0.005

--- Stream0108.g01 (geometry) ---

Geom Title=Existing Conditions

River Reach=Stream0108,Reach-1
Reach XY= 30
      1788475.00     13929375.00      1788334.68     13929514.23
      1788318.95     13929522.47      1788276.65     13929528.98
      1788258.33     13929541.65      1787884.79     13929914.48
      1787873.50     13929921.39      1787859.78     13929924.48
      1787795.10     13929925.25      1787776.60     13929928.86
      1787765.37     13929935.90      1787731.06     13929966.86
      1787714.49     13929973.77      1787594.99     13929974.98
      1787580.86     13929977.07      1787568.81     13929982.82
      1787548.13     13930001.17      1787338.64     13930211.80
      1787327.55     13930231.09      1787323.51     13930264.51
      1787319.25     13930277.54      1787308.50     13930292.05
      1787292.05     13930308.50      1787273.57     13930321.12
      1787231.09     13930327.55      1787218.97     13930333.17
      1787141.69     13930408.38      1787127.51     13930419.67
      1787106.88     13930425.07      1787075.00     13930425.00

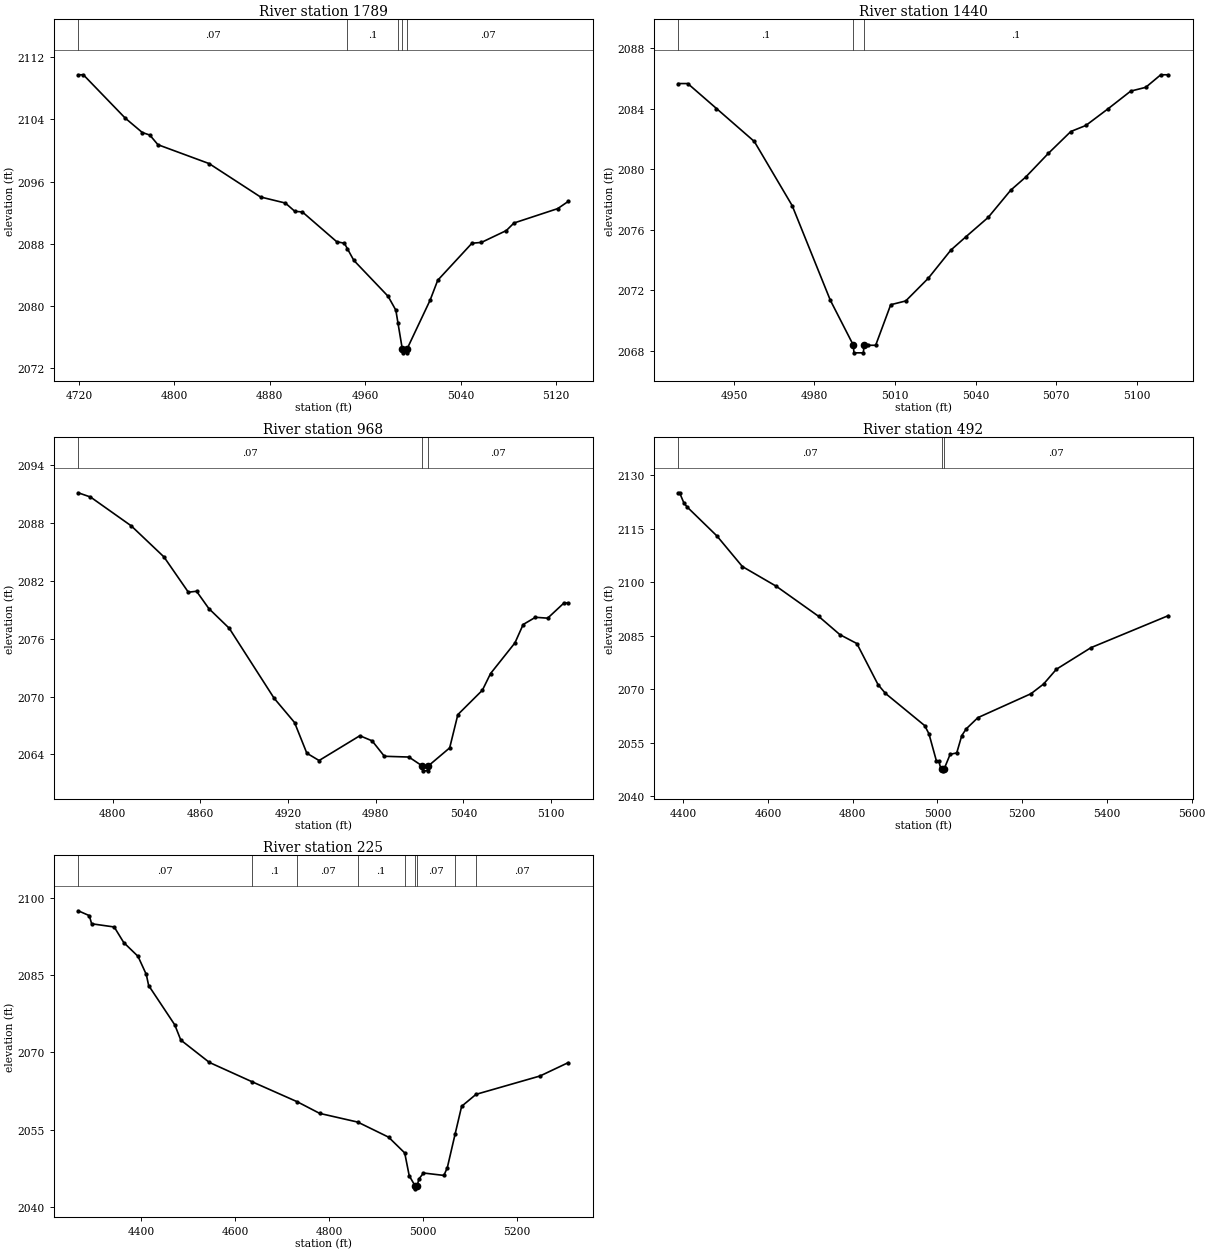
Type RM Length L Ch R = 1,1789,349,349,349
BEGIN DESCRIPTION:
Stream0108 4.0
END DESCRIPTION:
XS GIS Cut Line= 2
      1788261.99     13929193.31      1788522.14     13929510.98
#Sta/Elev= 30
  4719.5 2109.75  4723.8 2109.75  4758.9 2104.17  4773.2 2102.32  4779.5 2101.99
  4786.3 2100.75  4829.2 2098.32  4872.3 2094.02  4893.1 2093.24  4901.0 2092.18
  4907.4 2092.09  4936.1 2088.27  4942.6 2088.06  4945.1 2087.36  4950.5 2085.86
  4979.2 2081.24  4985.7 2079.45  4987.5 2077.79  4991.1 2074.46  4991.4 2073.96
  4994.9 2073.96  4995.1 2074.46  5014.4 2080.73  5020.8 2083.30  5049.5 2088.07
  5057.4 2088.17  5078.3 2089.70  5084.7 2090.67  5121.3 2092.52  5130.1 2093.44
#Mann=5,-1,0
  4719.5    0.07       0  4945.1     0.1       0  4987.5    0.07       0
  4991.1    0.05       0  4995.1    0.07       0
Bank Sta=4991.1,4995.1
Exp/Cntr=0.3,0.1

Type RM Length L Ch R = 1,1440,472,472,472
BEGIN DESCRIPTION:
Stream0108 3.0
END DESCRIPTION:
XS GIS Cut Line= 3
      1788124.99     13929574.99      1788175.00     13929625.00
      1788274.98     13929674.99
#Sta/Elev= 28
  4929.3 2085.66  4932.8 2085.66  4943.5 2084.01  4957.6 2081.83  4971.7 2077.59
  4985.9 2071.34  4994.5 2068.36  4994.7 2067.86  4998.2 2067.86  4998.5 2068.36
  5000.0 2068.36  5002.8 2068.36  5008.4 2071.04  5014.0 2071.29  5022.4 2072.79
  5030.8 2074.65  5036.4 2075.53  5044.7 2076.81  5053.1 2078.61  5058.7 2079.48
  5067.1 2081.04  5075.5 2082.49  5081.1 2082.89  5089.5 2084.01  5097.8 2085.16
  5103.4 2085.41  5109.0 2086.24  5111.8 2086.24
#Mann=3,-1,0
  4929.3     0.1       0  4994.5    0.05       0  4998.5     0.1       0
Bank Sta=4994.5,4998.5
Exp/Cntr=0.3,0.1

Type RM Length L Ch R = 1,968,476,476,476
BEGIN DESCRIPTION:
Stream0108 2.0
END DESCRIPTION:
XS GIS Cut Line= 3
      1787725.01     13929725.02      1787825.00     13929925.00
      1787925.01     13929975.01
#Sta/Elev= 30
  4776.3 2091.13  4784.7 2090.69  4812.6 2087.70  4835.0 2084.48  4851.7 2080.82
  4857.3 2080.92  4865.7 2079.13  4879.7 2077.08  4910.4 2069.83  4924.4 2067.31
  4932.8 2064.13  4941.2 2063.37  4969.1 2065.94  4977.5 2065.41  4985.9 2063.81
  5002.7 2063.73  5011.9 2062.80  5012.1 2062.30  5015.6 2062.30  5015.9 2062.80
  5030.6 2064.68  5036.2 2068.13  5053.0 2070.66  5058.6 2072.39  5075.3 2075.57
  5080.9 2077.47  5089.3 2078.22  5097.7 2078.13  5108.9 2079.71  5111.7 2079.71
#Mann=3,-1,0
  4776.3    0.07       0  5011.9    0.05       0  5015.9    0.07       0
Bank Sta=5011.9,5015.9
Exp/Cntr=0.3,0.1

Type RM Length L Ch R = 1,492,267,267,267
BEGIN DESCRIPTION:
Stream0108 1.0
END DESCRIPTION:
XS GIS Cut Line= 3
      1787450.42     13929514.18      1787425.00     13930125.00
      1787903.54     13930385.29
#Sta/Elev= 30
  4388.7 2125.02  4391.6 2125.02  4401.7 2122.18  4409.5 2121.03  4479.6 2112.94
  4539.7 2104.36  4619.7 2098.84  4719.8 2090.40  4769.9 2085.28  4809.9 2082.79
  4859.9 2071.28  4877.4 2068.82  4970.0 2059.80  4980.0 2057.52  4997.6 2049.92
  5002.9 2049.92  5008.1 2047.79  5011.8 2047.63  5012.1 2047.13  5015.8 2047.63
  5030.0 2051.75  5045.6 2052.16  5057.5 2057.00  5068.0 2058.89  5095.5 2062.03
  5220.9 2068.74  5250.5 2071.44  5280.8 2075.59  5362.5 2081.64  5544.8 2090.60
#Mann=3,-1,0
  4388.7    0.07       0  5011.8    0.05       0  5015.8    0.07       0
Bank Sta=5011.8,5015.8
Exp/Cntr=0.3,0.1

Type RM Length L Ch R = 1,225,0,0,0
BEGIN DESCRIPTION:
Stream0108 0.0
END DESCRIPTION:
XS GIS Cut Line= 4
      1787344.32     13929599.36      1787242.24     13930210.03
      1787282.65     13930436.52      1787417.16     13930577.69
#Sta/Elev= 30
  4265.3 2097.46  4288.9 2096.52  4293.9 2094.94  4342.0 2094.32  4362.3 2091.30
  4392.7 2088.63  4410.4 2085.11  4415.4 2082.97  4471.1 2075.34  4483.9 2072.40
  4544.8 2068.06  4634.9 2064.35  4732.2 2060.43  4779.9 2058.18  4861.1 2056.49
  4926.8 2053.57  4961.2 2050.51  4970.8 2046.09  4983.8 2044.05  4984.0 2043.55
  4987.8 2044.05  4991.1 2045.41  5001.2 2046.62  5044.7 2046.15  5052.0 2047.66
  5068.4 2054.09  5082.5 2059.55  5113.2 2061.87  5249.6 2065.43  5309.5 2068.01
#Mann=9,-1,0
  4265.3    0.07       0  4634.9     0.1       0  4732.2    0.07       0
  4861.1     0.1       0  4961.2    0.07       0  4983.8    0.05       0
  4987.8    0.07       0  5068.4     0.1       0  5113.2    0.07       0
Bank Sta=4983.8,4987.8
Exp/Cntr=0.3,0.1

Chan Stop Cuts=-1