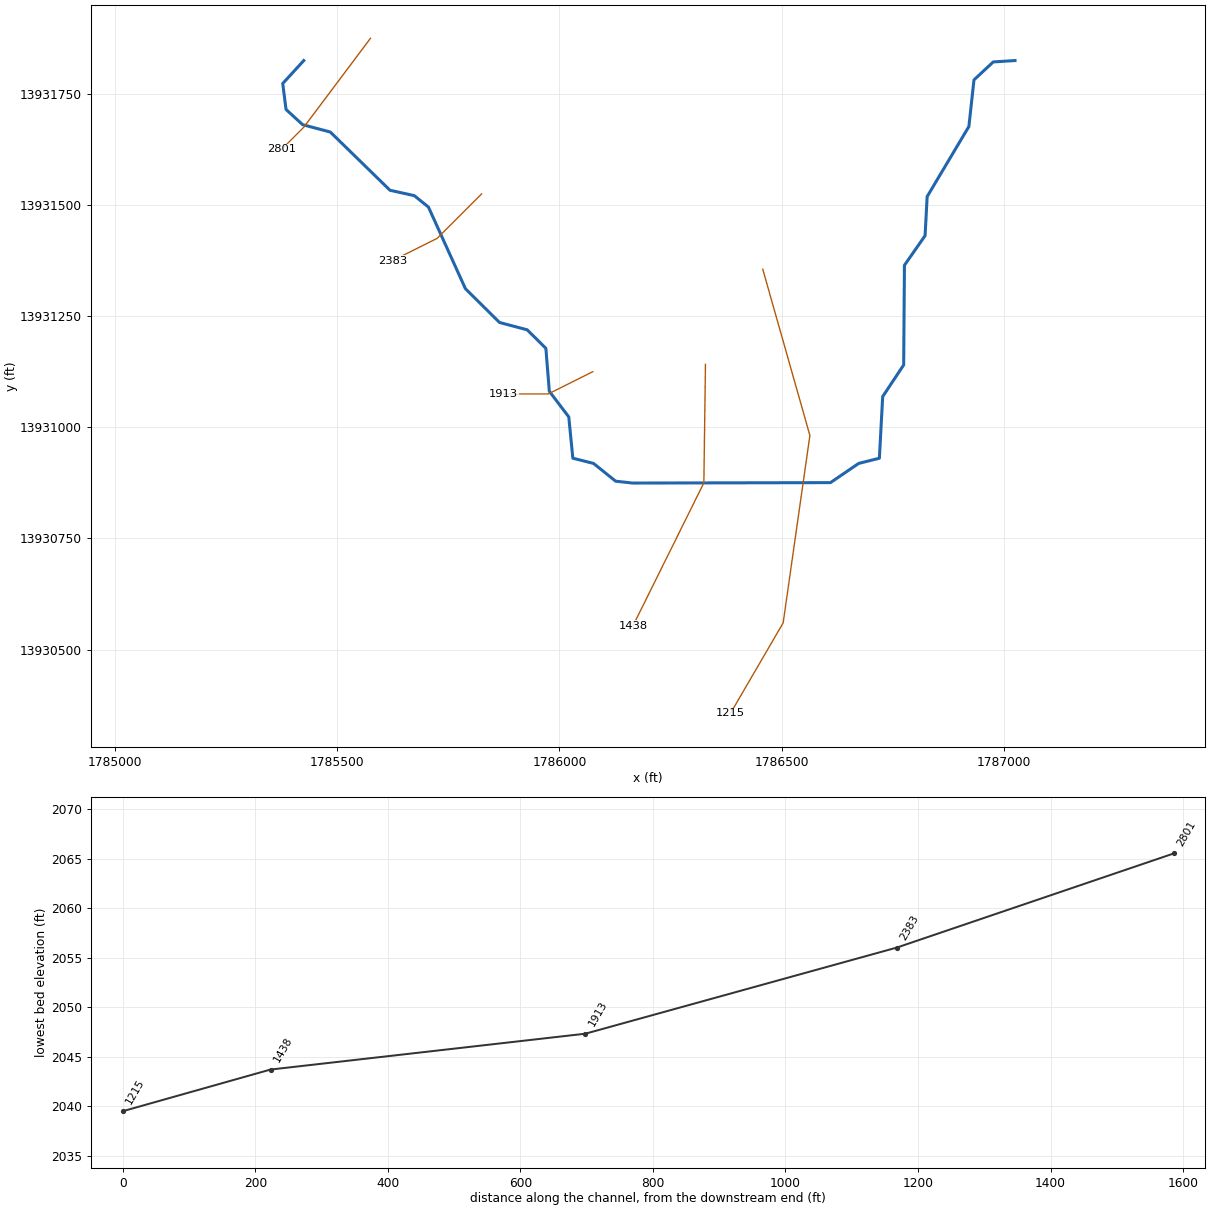
--- Stream0109.prj (project) ---

Proj Title=Stream0109 Base Level Engineering
Current Plan=p01
Default Exp/Contr=0.3,0.1
English Units
Geom File=g01
Flow File=f01
Plan File=p01
BEGIN DESCRIPTION:
Stream0109
END DESCRIPTION:

--- Stream0109.p01 (plan) ---

Plan Title=Multiple Run
Short Identifier=Multiple
Geom File=g01
Flow File=f01
Subcritical Flow
K Sum by GR= 0
Std Step Tol= 0.01
Critical Tol= 0.01
Num of Std Step Trials= 20
Max Error Tol= 0.3
Flow Tol Ratio= 0.001
Split Flow NTrial= 30
Split Flow Tol= 0.02
Split Flow Ratio= 0.02
Log Output Level= 0
Friction Slope Method= 1
Unsteady Friction Slope Method= 2
Unsteady Bridges Friction Slope Method= 1
Parabolic Critical Depth
Global Vel Dist=  1 , 1 , 1
Global Log Level= 0
CheckData=True
Encroach Param= -1, 0, 0, 0
BEGIN DESCRIPTION:
Multiple Run
END DESCRIPTION:

--- Stream0109.f01 (steady flow) ---

Flow Title=Multiple
Number of Profiles=7
Profile Names=10-year,25-year,50-year,1pct_min,100-year,1pct_plu,500-year
River Rch & RM= Stream0109,Reach-1,2801
     843    1429    1984    1332    2658    5304    4715
Boundary for River Rch & Prof#=Stream0109,Reach-1,1
Up Type=0
Dn Type=3
Dn Slope=0.005
Boundary for River Rch & Prof#=Stream0109,Reach-1,2
Up Type=0
Dn Type=3
Dn Slope=0.005
Boundary for River Rch & Prof#=Stream0109,Reach-1,3
Up Type=0
Dn Type=3
Dn Slope=0.005
Boundary for River Rch & Prof#=Stream0109,Reach-1,4
Up Type=0
Dn Type=3
Dn Slope=0.005
Boundary for River Rch & Prof#=Stream0109,Reach-1,5
Up Type=0
Dn Type=3
Dn Slope=0.005
Boundary for River Rch & Prof#=Stream0109,Reach-1,6
Up Type=0
Dn Type=3
Dn Slope=0.005
Boundary for River Rch & Prof#=Stream0109,Reach-1,7
Up Type=0
Dn Type=3
Dn Slope=0.005

--- Stream0109.g01 (geometry) ---

Geom Title=Existing Conditions

River Reach=Stream0109,Reach-1
Reach XY= 30
      1785425.00     13931825.00      1785377.65     13931773.34
      1785385.05     13931714.95      1785422.39     13931680.75
      1785484.66     13931664.21      1785618.97     13931533.17
      1785673.57     13931521.11      1785705.38     13931495.47
      1785788.61     13931311.76      1785865.32     13931235.78
      1785927.57     13931219.26      1785969.58     13931177.67
      1785977.36     13931080.98      1786021.11     13931023.33
      1786030.25     13930930.44      1786076.78     13930918.70
      1786126.52     13930878.74      1786164.81     13930874.54
      1786609.81     13930875.50      1786673.23     13930918.69
      1786719.82     13930930.41      1786727.28     13931069.05
      1786774.48     13931140.22      1786776.22     13931364.50
      1786822.64     13931430.98      1786827.33     13931519.03
      1786921.17     13931676.59      1786932.64     13931781.45
      1786975.99     13931821.88      1787025.00     13931825.00

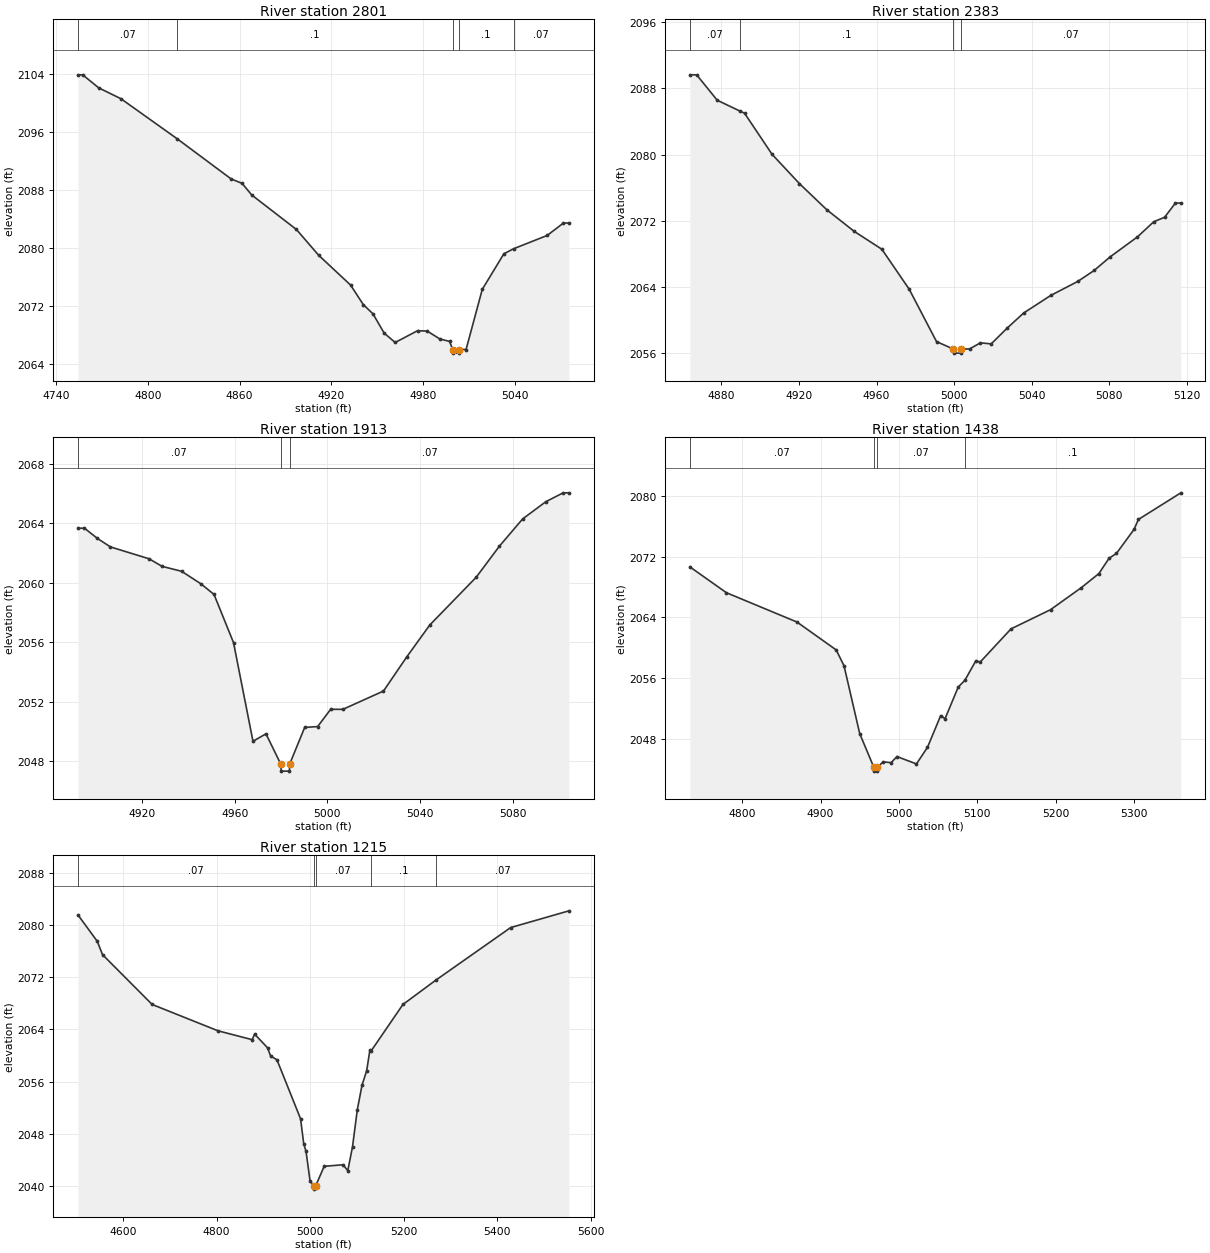
Type RM Length L Ch R = 1,2801,418,418,418
BEGIN DESCRIPTION:
Stream0109 4.0
END DESCRIPTION:
XS GIS Cut Line= 3
      1785574.97     13931874.97      1785425.00     13931675.00
      1785374.98     13931624.98
#Sta/Elev= 30
  4754.4 2103.91  4757.5 2103.91  4767.9 2102.12  4782.5 2100.61  4819.2 2095.09
  4854.4 2089.56  4861.6 2088.94  4867.9 2087.34  4897.1 2082.58  4911.6 2079.03
  4932.5 2074.91  4940.8 2072.21  4947.1 2070.95  4954.4 2068.29  4961.6 2067.00
  4976.2 2068.62  4982.5 2068.57  4990.8 2067.48  4997.1 2067.15  4999.2 2066.03
  4999.5 2065.53  5003.0 2065.53  5003.2 2066.03  5007.9 2066.03  5018.5 2074.33
  5032.6 2079.23  5038.9 2079.92  5060.9 2081.76  5071.5 2083.47  5075.1 2083.47
#Mann=5,-1,0
  4754.4    0.07       0  4819.2     0.1       0  4999.2    0.05       0
  5003.2     0.1       0  5038.9    0.07       0
Bank Sta=4999.2,5003.2
Exp/Cntr=0.3,0.1

Type RM Length L Ch R = 1,2383,470,470,470
BEGIN DESCRIPTION:
Stream0109 3.0
END DESCRIPTION:
XS GIS Cut Line= 3
      1785824.97     13931524.97      1785725.00     13931425.00
      1785624.98     13931374.99
#Sta/Elev= 30
  4863.7 2089.64  4867.2 2089.64  4877.8 2086.57  4889.8 2085.23  4891.9 2085.00
  4906.1 2080.03  4920.2 2076.50  4934.4 2073.32  4948.5 2070.72  4962.7 2068.57
  4976.8 2063.74  4990.9 2057.41  4999.5 2056.52  4999.8 2056.02  5003.3 2056.02
  5003.5 2056.52  5007.9 2056.52  5013.5 2057.26  5019.1 2057.14  5027.4 2059.06
  5035.8 2060.86  5049.8 2062.99  5063.8 2064.69  5072.2 2066.01  5080.5 2067.66
  5094.5 2070.06  5102.9 2071.89  5108.5 2072.43  5114.1 2074.15  5116.9 2074.15
#Mann=4,-1,0
  4863.7    0.07       0  4889.8     0.1       0  4999.5    0.05       0
  5003.5    0.07       0
Bank Sta=4999.5,5003.5
Exp/Cntr=0.3,0.1

Type RM Length L Ch R = 1,1913,475,475,475
BEGIN DESCRIPTION:
Stream0109 2.0
END DESCRIPTION:
XS GIS Cut Line= 3
      1786075.00     13931125.00      1785975.00     13931075.00
      1785875.00     13931075.00
#Sta/Elev= 29
  4892.4 2063.67  4895.2 2063.67  4900.8 2062.98  4906.4 2062.41  4923.1 2061.61
  4928.7 2061.10  4937.1 2060.77  4945.5 2059.92  4951.1 2059.21  4959.5 2055.97
  4967.9 2049.33  4973.5 2049.83  4979.8 2047.82  4980.1 2047.32  4983.6 2047.32
  4983.8 2047.82  4990.2 2050.26  4995.8 2050.32  5001.4 2051.48  5006.7 2051.48
  5024.2 2052.71  5034.2 2055.00  5044.2 2057.16  5064.2 2060.37  5074.2 2062.46
  5084.2 2064.29  5094.2 2065.45  5101.7 2066.05  5104.2 2066.05
#Mann=3,-1,0
  4892.4    0.07       0  4979.8    0.05       0  4983.8    0.07       0
Bank Sta=4979.8,4983.8
Exp/Cntr=0.3,0.1

Type RM Length L Ch R = 1,1438,223,223,223
BEGIN DESCRIPTION:
Stream0109 1.0
END DESCRIPTION:
XS GIS Cut Line= 3
      1786328.60     13931141.56      1786325.00     13930875.00
      1786165.27     13930552.91
#Sta/Elev= 30
  4733.4 2070.65  4780.0 2067.24  4870.0 2063.37  4920.0 2059.69  4930.0 2057.59
  4950.0 2048.64  4968.0 2044.20  4968.2 2043.70  4971.7 2043.70  4972.0 2044.20
  4980.0 2044.92  4990.0 2044.82  4997.5 2045.62  5022.3 2044.65  5036.4 2046.84
  5053.2 2051.02  5058.8 2050.62  5075.6 2054.79  5084.1 2055.69  5098.1 2058.27
  5103.6 2058.09  5142.9 2062.47  5193.3 2065.00  5232.6 2067.91  5255.0 2069.77
  5267.9 2071.78  5277.4 2072.43  5299.8 2075.60  5305.4 2076.91  5359.5 2080.42
#Mann=4,-1,0
  4733.4    0.07       0  4968.0    0.05       0  4972.0    0.07       0
  5084.1     0.1       0
Bank Sta=4968,4972
Exp/Cntr=0.3,0.1

Type RM Length L Ch R = 1,1215,0,0,0
BEGIN DESCRIPTION:
Stream0109 0.0
END DESCRIPTION:
XS GIS Cut Line= 4
      1786457.52     13931355.49      1786563.53     13930981.57
      1786503.35     13930559.91      1786384.79     13930356.42
#Sta/Elev= 30
  4503.5 2081.56  4544.8 2077.51  4556.0 2075.47  4662.2 2067.82  4803.1 2063.78
  4876.1 2062.42  4881.3 2063.28  4908.9 2061.18  4915.5 2059.92  4929.1 2059.33
  4979.6 2050.28  4986.3 2046.47  4991.3 2045.28  4999.8 2040.78  5007.9 2039.99
  5008.2 2039.49  5011.9 2039.99  5030.1 2042.99  5070.5 2043.23  5080.6 2042.32
  5090.7 2045.98  5100.8 2051.60  5110.9 2055.40  5121.0 2057.67  5127.8 2060.80
  5129.8 2060.62  5198.5 2067.82  5268.8 2071.55  5428.9 2079.62  5553.6 2082.19
#Mann=5,-1,0
  4503.5    0.07       0  5007.9    0.05       0  5011.9    0.07       0
  5129.8     0.1       0  5268.8    0.07       0
Bank Sta=5007.9,5011.9
Exp/Cntr=0.3,0.1

Chan Stop Cuts=-1