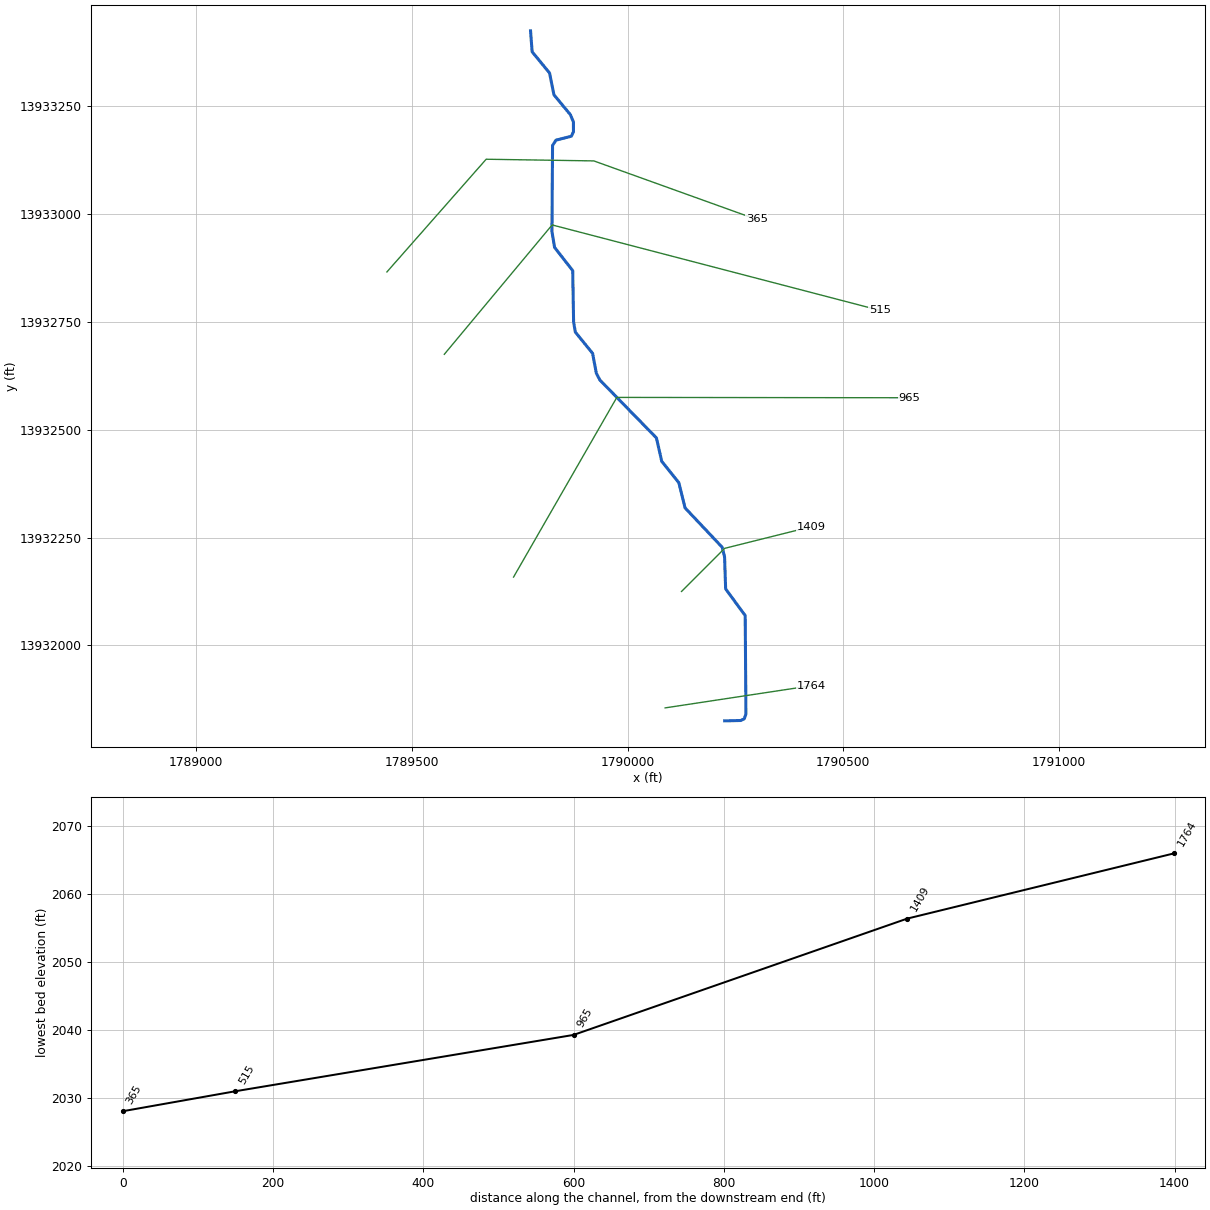
--- Stream0111.prj (project) ---

Proj Title=Stream0111 Base Level Engineering
Current Plan=p01
Default Exp/Contr=0.3,0.1
English Units
Geom File=g01
Flow File=f01
Plan File=p01
BEGIN DESCRIPTION:
Stream0111
END DESCRIPTION:

--- Stream0111.p01 (plan) ---

Plan Title=Multiple Run
Short Identifier=Multiple
Geom File=g01
Flow File=f01
Subcritical Flow
K Sum by GR= 0
Std Step Tol= 0.01
Critical Tol= 0.01
Num of Std Step Trials= 20
Max Error Tol= 0.3
Flow Tol Ratio= 0.001
Split Flow NTrial= 30
Split Flow Tol= 0.02
Split Flow Ratio= 0.02
Log Output Level= 0
Friction Slope Method= 1
Unsteady Friction Slope Method= 2
Unsteady Bridges Friction Slope Method= 1
Parabolic Critical Depth
Global Vel Dist=  1 , 1 , 1
Global Log Level= 0
CheckData=True
Encroach Param= -1, 0, 0, 0
BEGIN DESCRIPTION:
Multiple Run
END DESCRIPTION:

--- Stream0111.f01 (steady flow) ---

Flow Title=Multiple
Number of Profiles=7
Profile Names=10-year,25-year,50-year,1pct_min,100-year,1pct_plu,500-year
River Rch & RM= Stream0111,Reach-1,1764
     352     563     753     489     977    1949    1616
Boundary for River Rch & Prof#=Stream0111,Reach-1,1
Up Type=0
Dn Type=3
Dn Slope=0.005
Boundary for River Rch & Prof#=Stream0111,Reach-1,2
Up Type=0
Dn Type=3
Dn Slope=0.005
Boundary for River Rch & Prof#=Stream0111,Reach-1,3
Up Type=0
Dn Type=3
Dn Slope=0.005
Boundary for River Rch & Prof#=Stream0111,Reach-1,4
Up Type=0
Dn Type=3
Dn Slope=0.005
Boundary for River Rch & Prof#=Stream0111,Reach-1,5
Up Type=0
Dn Type=3
Dn Slope=0.005
Boundary for River Rch & Prof#=Stream0111,Reach-1,6
Up Type=0
Dn Type=3
Dn Slope=0.005
Boundary for River Rch & Prof#=Stream0111,Reach-1,7
Up Type=0
Dn Type=3
Dn Slope=0.005

--- Stream0111.g01 (geometry) ---

Geom Title=Existing Conditions

River Reach=Stream0111,Reach-1
Reach XY= 30
      1790225.00     13931825.00      1790262.57     13931825.83
      1790270.37     13931829.63      1790274.39     13931840.61
      1790272.74     13932069.06      1790227.36     13932130.98
      1790224.87     13932204.95      1790219.46     13932227.42
      1790133.16     13932318.95      1790118.90     13932377.19
      1790079.19     13932426.74      1790066.86     13932481.06
      1789935.76     13932615.32      1789927.50     13932631.03
      1789918.86     13932677.17      1789878.76     13932726.56
      1789874.81     13932749.92      1789872.73     13932869.06
      1789830.75     13932922.67      1789824.57     13932959.82
      1789826.00     13933159.06      1789833.68     13933171.45
      1789869.79     13933180.79      1789874.48     13933191.14
      1789874.34     13933213.96      1789867.33     13933230.66
      1789829.22     13933276.69      1789819.06     13933327.25
      1789778.60     13933376.49      1789775.00     13933425.00

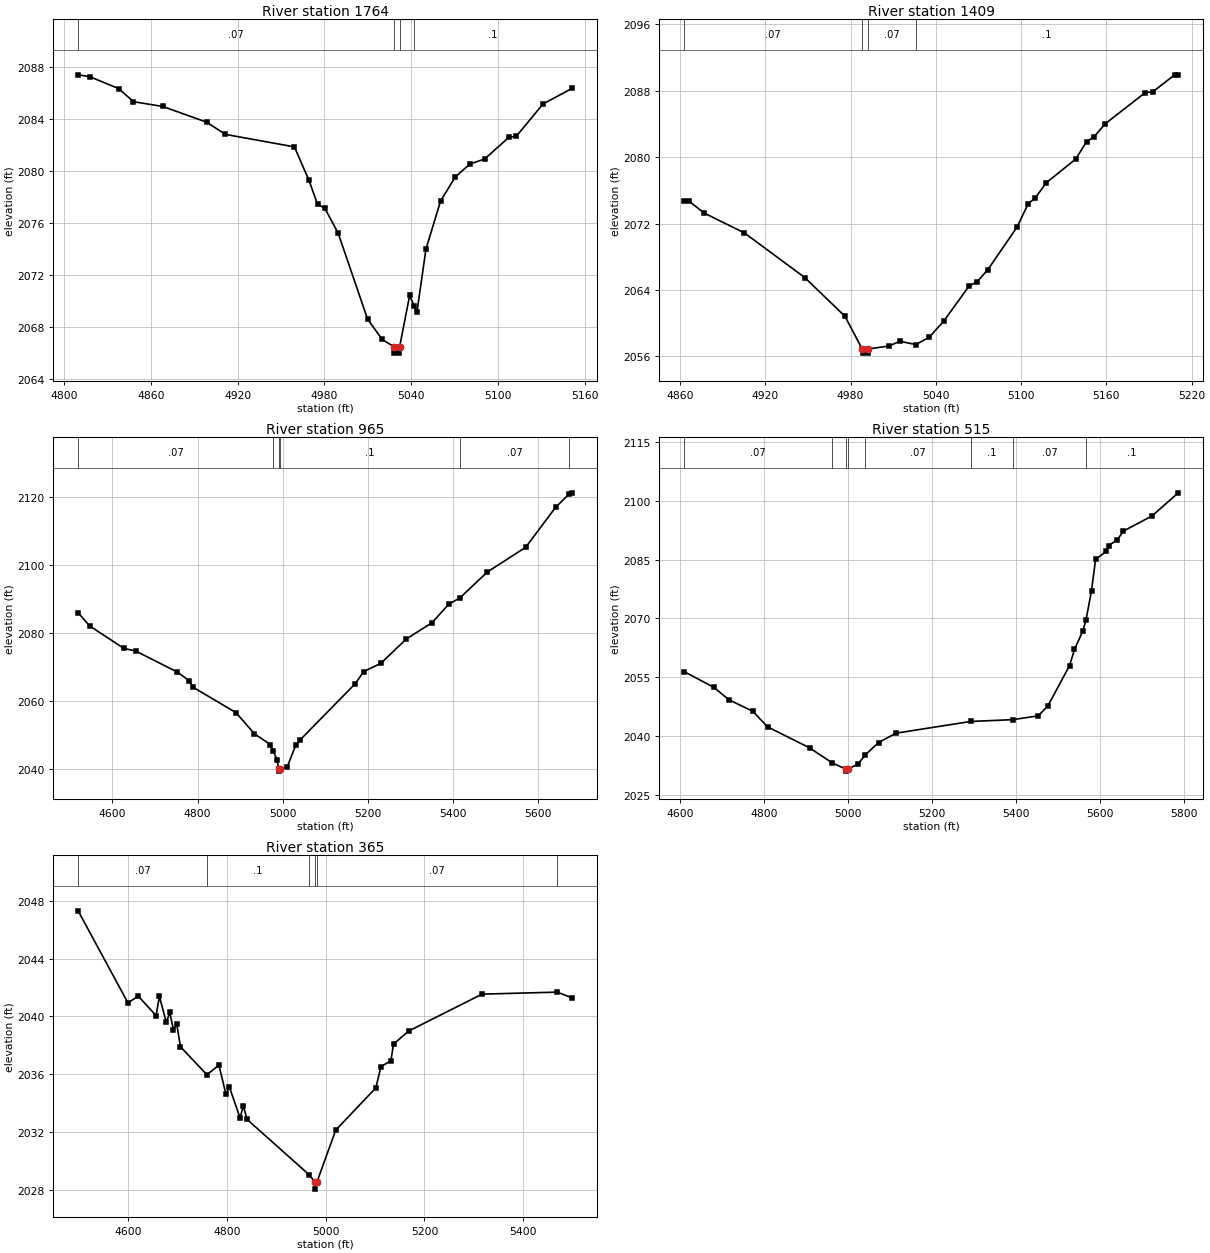
Type RM Length L Ch R = 1,1764,355,355,355
BEGIN DESCRIPTION:
Stream0111 4.0
END DESCRIPTION:
XS GIS Cut Line= 2
      1790087.09     13931855.07      1790424.93     13931906.27
#Sta/Elev= 30
  4809.6 2087.41  4817.6 2087.27  4837.6 2086.35  4847.9 2085.34  4868.2 2084.97
  4898.5 2083.76  4911.5 2082.82  4959.2 2081.86  4969.3 2079.27  4975.2 2077.43
  4980.2 2077.14  4989.5 2075.20  5009.8 2068.59  5019.9 2067.02  5028.0 2066.47
  5028.2 2065.97  5031.7 2065.97  5032.0 2066.47  5038.9 2070.42  5042.0 2069.60
  5043.9 2069.10  5050.2 2074.00  5060.3 2077.69  5070.5 2079.55  5080.6 2080.54
  5090.7 2080.92  5107.6 2082.60  5112.7 2082.68  5131.1 2085.16  5151.3 2086.37
#Mann=4,-1,0
  4809.6    0.07       0  5028.0    0.05       0  5032.0    0.07       0
  5042.0     0.1       0
Bank Sta=5028,5032
Exp/Cntr=0.3,0.1

Type RM Length L Ch R = 1,1409,444,444,444
BEGIN DESCRIPTION:
Stream0111 3.0
END DESCRIPTION:
XS GIS Cut Line= 3
      1790125.03     13932125.03      1790225.00     13932225.00
      1790424.97     13932274.99
#Sta/Elev= 30
  4863.0 2074.68  4866.5 2074.68  4877.1 2073.26  4905.4 2070.86  4947.8 2065.49
  4976.1 2060.82  4988.2 2056.88  4988.5 2056.38  4992.0 2056.38  4992.2 2056.88
  5006.9 2057.23  5014.7 2057.81  5025.9 2057.41  5035.3 2058.29  5045.6 2060.24
  5063.6 2064.52  5068.8 2064.94  5076.5 2066.42  5097.1 2071.56  5104.9 2074.36
  5110.0 2075.10  5117.8 2076.93  5138.4 2079.77  5146.1 2081.88  5151.3 2082.45
  5159.0 2084.00  5187.3 2087.78  5192.5 2087.86  5208.0 2089.92  5210.5 2089.92
#Mann=4,-1,0
  4863.0    0.07       0  4988.2    0.05       0  4992.2    0.07       0
  5025.9     0.1       0
Bank Sta=4988.2,4992.2
Exp/Cntr=0.3,0.1

Type RM Length L Ch R = 1,965,450,450,450
BEGIN DESCRIPTION:
Stream0111 2.0
END DESCRIPTION:
XS GIS Cut Line= 3
      1789735.53     13932158.38      1789975.00     13932575.00
      1790654.06     13932574.22
#Sta/Elev= 30
  4519.7 2085.90  4546.7 2082.02  4627.2 2075.38  4654.5 2074.65  4750.8 2068.54
  4781.1 2065.86  4788.2 2064.06  4890.3 2056.49  4933.4 2050.28  4970.8 2047.11
  4977.7 2045.13  4986.6 2042.65  4990.3 2039.78  4990.6 2039.28  4994.3 2039.78
  5010.2 2040.42  5030.2 2046.83  5040.2 2048.39  5170.2 2065.02  5190.2 2068.59
  5230.2 2070.99  5290.2 2078.18  5350.2 2082.93  5390.2 2088.47  5415.7 2090.23
  5480.2 2097.88  5570.2 2105.14  5640.2 2116.87  5671.4 2120.72  5679.3 2121.17
#Mann=6,-1,0
  4519.7    0.07       0  4977.7     0.1       0  4990.3    0.05       0
  4994.3     0.1       0  5415.7    0.07       0  5671.4     0.1       0
Bank Sta=4990.3,4994.3
Exp/Cntr=0.3,0.1

Type RM Length L Ch R = 1,515,150,150,150
BEGIN DESCRIPTION:
Stream0111 1.0
END DESCRIPTION:
XS GIS Cut Line= 3
      1789574.99     13932674.98      1789825.00     13932975.00
      1790585.34     13932776.73
#Sta/Elev= 30
  4610.1 2056.42  4681.1 2052.37  4716.2 2049.26  4773.5 2046.28  4808.6 2042.31
  4908.9 2036.93  4962.7 2033.10  4995.4 2031.50  4995.6 2031.00  4999.4 2031.50
  5023.5 2032.75  5041.7 2035.19  5073.0 2038.31  5114.3 2040.69  5292.2 2043.69
  5392.5 2044.15  5453.3 2045.13  5476.0 2047.66  5527.7 2057.96  5539.4 2062.08
  5558.7 2066.67  5566.6 2069.51  5579.9 2077.09  5589.7 2085.13  5615.2 2087.13
  5620.7 2088.60  5641.4 2090.09  5655.7 2092.31  5724.0 2096.19  5786.4 2102.09
#Mann=8,-1,0
  4610.1    0.07       0  4962.7     0.1       0  4995.4    0.05       0
  4999.4     0.1       0  5041.7    0.07       0  5292.2     0.1       0
  5392.5    0.07       0  5566.6     0.1       0
Bank Sta=4995.4,4999.4
Exp/Cntr=0.3,0.1

Type RM Length L Ch R = 1,365,0,0,0
BEGIN DESCRIPTION:
Stream0111 0.0
END DESCRIPTION:
XS GIS Cut Line= 4
      1789441.92     13932865.96      1789672.04     13933127.30
      1789921.75     13933123.43      1790299.61     13932987.58
#Sta/Elev= 30
  4499.3 2047.30  4600.1 2040.94  4621.0 2041.40  4657.0 2040.06  4663.7 2041.38
  4677.9 2039.58  4684.6 2040.28  4692.2 2039.08  4698.8 2039.47  4706.4 2037.90
  4759.9 2035.97  4784.2 2036.63  4798.4 2034.61  4805.1 2035.14  4826.9 2032.99
  4833.5 2033.81  4841.1 2032.88  4966.1 2029.07  4978.5 2028.56  4978.7 2028.06
  4982.5 2028.56  5020.5 2032.14  5101.6 2035.06  5112.0 2036.53  5132.1 2036.94
  5137.4 2038.09  5168.1 2038.99  5316.4 2041.54  5468.5 2041.68  5498.8 2041.28
#Mann=6,-1,0
  4499.3    0.07       0  4759.9     0.1       0  4966.1    0.07       0
  4978.5    0.05       0  4982.5    0.07       0  5468.5     0.1       0
Bank Sta=4978.5,4982.5
Exp/Cntr=0.3,0.1

Chan Stop Cuts=-1