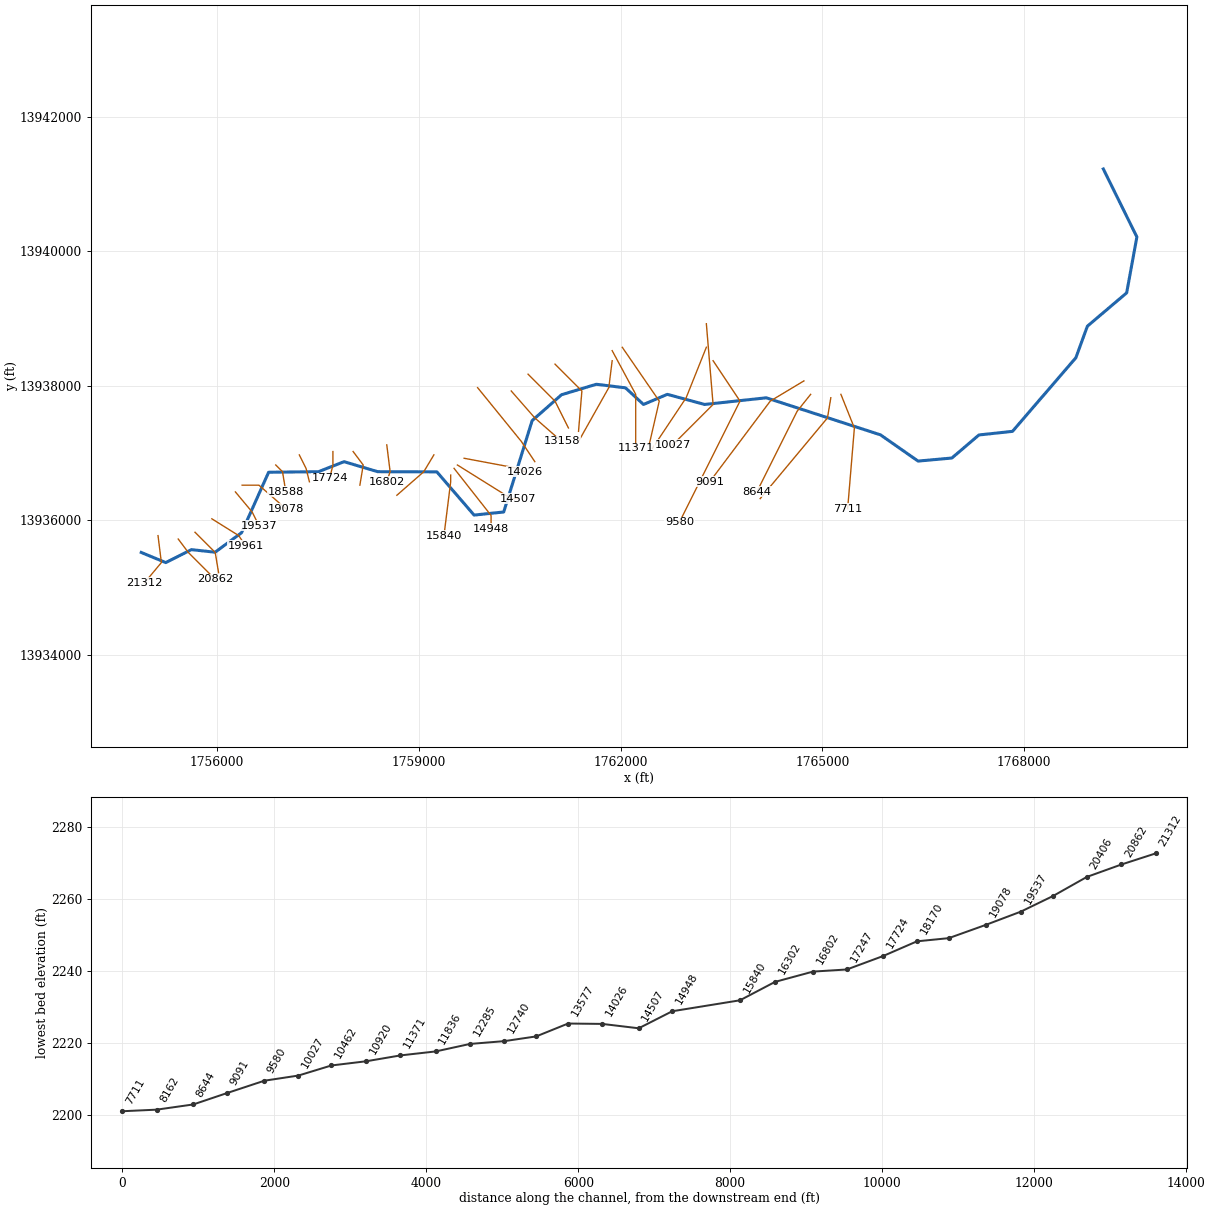
--- Stream0112.prj (project) ---

Proj Title=Stream0112 Base Level Engineering
Current Plan=p01
Default Exp/Contr=0.3,0.1
English Units
Geom File=g01
Flow File=f01
Plan File=p01
BEGIN DESCRIPTION:
Stream0112
END DESCRIPTION:

--- Stream0112.p01 (plan) ---

Plan Title=Multiple Run
Short Identifier=Multiple
Geom File=g01
Flow File=f01
Subcritical Flow
K Sum by GR= 0
Std Step Tol= 0.01
Critical Tol= 0.01
Num of Std Step Trials= 20
Max Error Tol= 0.3
Flow Tol Ratio= 0.001
Split Flow NTrial= 30
Split Flow Tol= 0.02
Split Flow Ratio= 0.02
Log Output Level= 0
Friction Slope Method= 1
Unsteady Friction Slope Method= 2
Unsteady Bridges Friction Slope Method= 1
Parabolic Critical Depth
Global Vel Dist=  1 , 1 , 1
Global Log Level= 0
CheckData=True
Encroach Param= -1, 0, 0, 0
BEGIN DESCRIPTION:
Multiple Run
END DESCRIPTION:

--- Stream0112.f01 (steady flow) ---

Flow Title=Multiple
Number of Profiles=7
Profile Names=10-year,25-year,50-year,1pct_min,100-year,1pct_plu,500-year
River Rch & RM= Stream0112,Reach-1,21312
    1345    2322    3256    2202    4393    8765    7918
River Rch & RM= Stream0112,Reach-1,18588
    1606    2796    3942    2677    5342   10659    9717
River Rch & RM= Stream0112,Reach-1,14948
    2420    4285    6111    4192    8363   16687   15521
River Rch & RM= Stream0112,Reach-1,10027
    2754    4904    7021    4832    9641   19235   18014
River Rch & RM= Stream0112,Reach-1,9091
    3039    5430    7792    5373   10721   21391   20114
River Rch & RM= Stream0112,Reach-1,6812
    3130    5598    8040    5547   11069   22085   20793
River Rch & RM= Stream0112,Reach-1,4568
    4334    7818   11293    7832   15626   31179   29638
Boundary for River Rch & Prof#=Stream0112,Reach-1,1
Up Type=0
Dn Type=3
Dn Slope=0.005
Boundary for River Rch & Prof#=Stream0112,Reach-1,2
Up Type=0
Dn Type=3
Dn Slope=0.005
Boundary for River Rch & Prof#=Stream0112,Reach-1,3
Up Type=0
Dn Type=3
Dn Slope=0.005
Boundary for River Rch & Prof#=Stream0112,Reach-1,4
Up Type=0
Dn Type=3
Dn Slope=0.005
Boundary for River Rch & Prof#=Stream0112,Reach-1,5
Up Type=0
Dn Type=3
Dn Slope=0.005
Boundary for River Rch & Prof#=Stream0112,Reach-1,6
Up Type=0
Dn Type=3
Dn Slope=0.005
Boundary for River Rch & Prof#=Stream0112,Reach-1,7
Up Type=0
Dn Type=3
Dn Slope=0.005

--- Stream0112.g01 (geometry) ---

Geom Title=Existing Conditions

River Reach=Stream0112,Reach-1
Reach XY= 30
      1754875.00     13935525.00      1755240.20     13935374.51
      1755621.70     13935566.92      1755973.50     13935528.46
      1756367.15     13935818.81      1756768.81     13936717.17
      1757509.73     13936725.38      1757890.22     13936874.48
      1758390.16     13936725.39      1759269.15     13936722.94
      1759822.55     13936080.46      1760263.15     13936126.73
      1760685.63     13937485.00      1761122.57     13937869.48
      1761640.39     13938024.92      1762073.28     13937971.66
      1762340.21     13937724.90      1762694.98     13937875.04
      1763249.91     13937724.74      1764164.50     13937823.80
      1765863.03     13937273.02      1766421.67     13936883.01
      1766923.75     13936928.45      1767326.50     13937271.39
      1767825.00     13937325.00      1768766.86     13938418.94
      1768938.26     13938888.65      1769521.84     13939383.32
      1769673.78     13940214.50      1769175.00     13941225.00

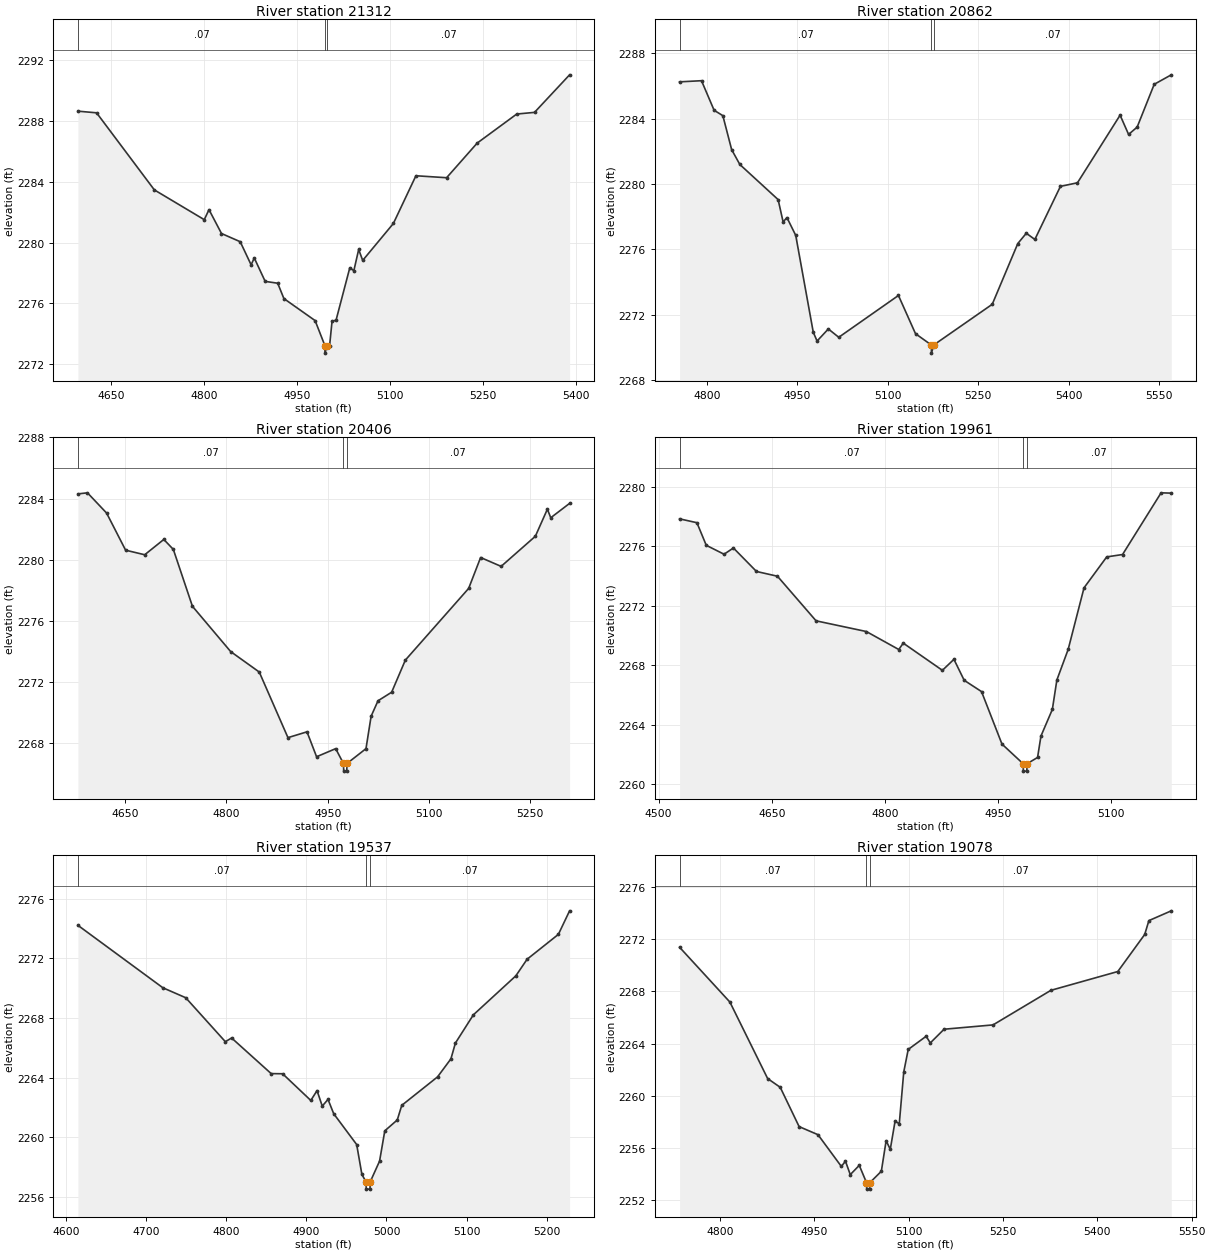
Type RM Length L Ch R = 1,21312,450,450,450
BEGIN DESCRIPTION:
Stream0112 45.0
END DESCRIPTION:
XS GIS Cut Line= 3
      1755125.00     13935774.97      1755175.00     13935375.00
      1754925.00     13935075.00
#Sta/Elev= 30
  4596.7 2288.65  4626.9 2288.54  4720.1 2283.47  4800.7 2281.51  4808.3 2282.17
  4828.5 2280.60  4858.7 2280.06  4876.3 2278.54  4881.4 2278.99  4899.0 2277.45
  4919.2 2277.33  4929.2 2276.32  4979.6 2274.87  4995.3 2273.23  4995.5 2272.73
  4999.3 2273.23  5003.0 2273.23  5006.9 2274.82  5013.4 2274.90  5035.6 2278.35
  5042.1 2278.15  5049.9 2279.55  5056.4 2278.83  5105.9 2281.26  5142.3 2284.40
  5191.8 2284.27  5241.2 2286.55  5305.0 2288.46  5333.7 2288.57  5390.3 2291.04
#Mann=3,-1,0
  4596.7    0.07       0  4995.3    0.05       0  4999.3    0.07       0
Bank Sta=4995.3,4999.3
Exp/Cntr=0.3,0.1

Type RM Length L Ch R = 1,20862,456,456,456
BEGIN DESCRIPTION:
Stream0112 44.0
END DESCRIPTION:
XS GIS Cut Line= 3
      1755425.02     13935724.98      1755575.00     13935525.00
      1755975.03     13935124.97
#Sta/Elev= 30
  4754.6 2286.26  4791.0 2286.33  4811.9 2284.52  4826.4 2284.19  4841.0 2282.11
  4854.6 2281.20  4918.1 2279.05  4926.4 2277.68  4932.7 2277.95  4947.3 2276.86
  4976.4 2270.93  4982.7 2270.39  5001.4 2271.13  5018.7 2270.62  5117.7 2273.18
  5146.0 2270.84  5172.2 2270.15  5172.5 2269.65  5176.3 2270.15  5273.3 2272.64
  5315.7 2276.36  5329.8 2276.99  5344.0 2276.61  5386.4 2279.86  5414.7 2280.08
  5485.4 2284.22  5499.5 2283.04  5513.7 2283.49  5542.0 2286.11  5570.3 2286.69
#Mann=3,-1,0
  4754.6    0.07       0  5172.2    0.05       0  5176.3    0.07       0
Bank Sta=5172.2,5176.3
Exp/Cntr=0.3,0.1

Type RM Length L Ch R = 1,20406,445,445,445
BEGIN DESCRIPTION:
Stream0112 43.0
END DESCRIPTION:
XS GIS Cut Line= 3
      1755674.98     13935825.02      1755975.00     13935525.00
      1756025.00     13935225.03
#Sta/Elev= 30
  4579.9 2284.31  4594.1 2284.38  4622.4 2283.06  4650.6 2280.63  4678.9 2280.33
  4707.2 2281.33  4721.3 2280.68  4749.6 2276.96  4806.2 2274.00  4848.6 2272.66
  4891.1 2268.37  4919.3 2268.75  4933.5 2267.12  4961.8 2267.65  4973.3 2266.68
  4973.7 2266.18  4978.2 2266.18  4978.6 2266.68  5006.7 2267.65  5014.3 2269.77
  5024.5 2270.78  5044.7 2271.34  5065.0 2273.44  5158.8 2278.13  5176.5 2280.15
  5206.9 2279.57  5257.6 2281.54  5275.4 2283.31  5280.4 2282.75  5308.3 2283.69
#Mann=3,-1,0
  4579.9    0.07       0  4973.3    0.05       0  4978.6    0.07       0
Bank Sta=4973.3,4978.6
Exp/Cntr=0.3,0.1

Type RM Length L Ch R = 1,19961,424,424,424
BEGIN DESCRIPTION:
Stream0112 42.0
END DESCRIPTION:
XS GIS Cut Line= 3
      1755924.97     13936025.02      1756325.00     13935775.00
      1756424.99     13935625.01
#Sta/Elev= 30
  4527.8 2277.84  4550.8 2277.58  4563.2 2276.06  4586.8 2275.46  4599.2 2275.88
  4629.8 2274.30  4657.6 2273.98  4708.8 2270.98  4775.5 2270.26  4818.5 2269.05
  4824.4 2269.48  4876.3 2267.65  4891.6 2268.39  4905.2 2266.98  4928.2 2266.22
  4955.3 2262.69  4983.3 2261.37  4983.7 2260.87  4988.2 2260.87  4988.7 2261.37
  5002.5 2261.79  5007.0 2263.23  5022.1 2265.02  5028.1 2267.00  5043.1 2269.06
  5064.1 2273.20  5094.2 2275.28  5115.2 2275.44  5166.3 2279.59  5179.8 2279.57
#Mann=3,-1,0
  4527.8    0.07       0  4983.3    0.05       0  4988.7    0.07       0
Bank Sta=4983.3,4988.7
Exp/Cntr=0.3,0.1

Type RM Length L Ch R = 1,19537,459,459,459
BEGIN DESCRIPTION:
Stream0112 41.0
END DESCRIPTION:
XS GIS Cut Line= 3
      1756275.02     13936424.97      1756525.00     13936125.00
      1756625.01     13935924.98
#Sta/Elev= 30
  4614.6 2274.22  4720.7 2270.03  4749.3 2269.36  4798.8 2266.41  4806.6 2266.66
  4856.0 2264.27  4870.3 2264.26  4905.5 2262.47  4913.3 2263.13  4919.8 2262.09
  4927.0 2262.54  4934.1 2261.58  4962.8 2259.51  4969.3 2257.51  4974.3 2257.02
  4974.8 2256.52  4979.4 2256.52  4979.8 2257.02  4991.4 2258.40  4997.9 2260.43
  5013.5 2261.16  5019.1 2262.14  5063.8 2264.05  5080.5 2265.26  5086.1 2266.32
  5108.5 2268.21  5161.6 2270.83  5175.6 2271.94  5214.7 2273.61  5228.7 2275.19
#Mann=3,-1,0
  4614.6    0.07       0  4974.3    0.05       0  4979.8    0.07       0
Bank Sta=4974.3,4979.8
Exp/Cntr=0.3,0.1

Type RM Length L Ch R = 1,19078,490,490,490
BEGIN DESCRIPTION:
Stream0112 40.0
END DESCRIPTION:
XS GIS Cut Line= 3
      1756375.01     13936525.00      1756625.00     13936525.00
      1757025.01     13936174.99
#Sta/Elev= 30
  4736.1 2271.38  4816.1 2267.18  4876.1 2261.32  4896.1 2260.65  4926.1 2257.64
  4956.1 2257.02  4993.2 2254.59  4999.8 2254.99  5007.4 2253.96  5021.7 2254.67
  5033.2 2253.35  5033.6 2252.85  5038.2 2252.85  5038.7 2253.35  5056.8 2254.22
  5064.4 2256.56  5071.0 2255.90  5078.6 2258.05  5085.3 2257.86  5092.4 2261.82
  5099.5 2263.55  5128.0 2264.56  5134.6 2264.05  5156.5 2265.10  5234.3 2265.43
  5326.3 2268.08  5432.6 2269.52  5475.4 2272.36  5482.0 2273.42  5517.6 2274.17
#Mann=3,-1,0
  4736.1    0.07       0  5033.2    0.05       0  5038.7    0.07       0
Bank Sta=5033.2,5038.7
Exp/Cntr=0.3,0.1

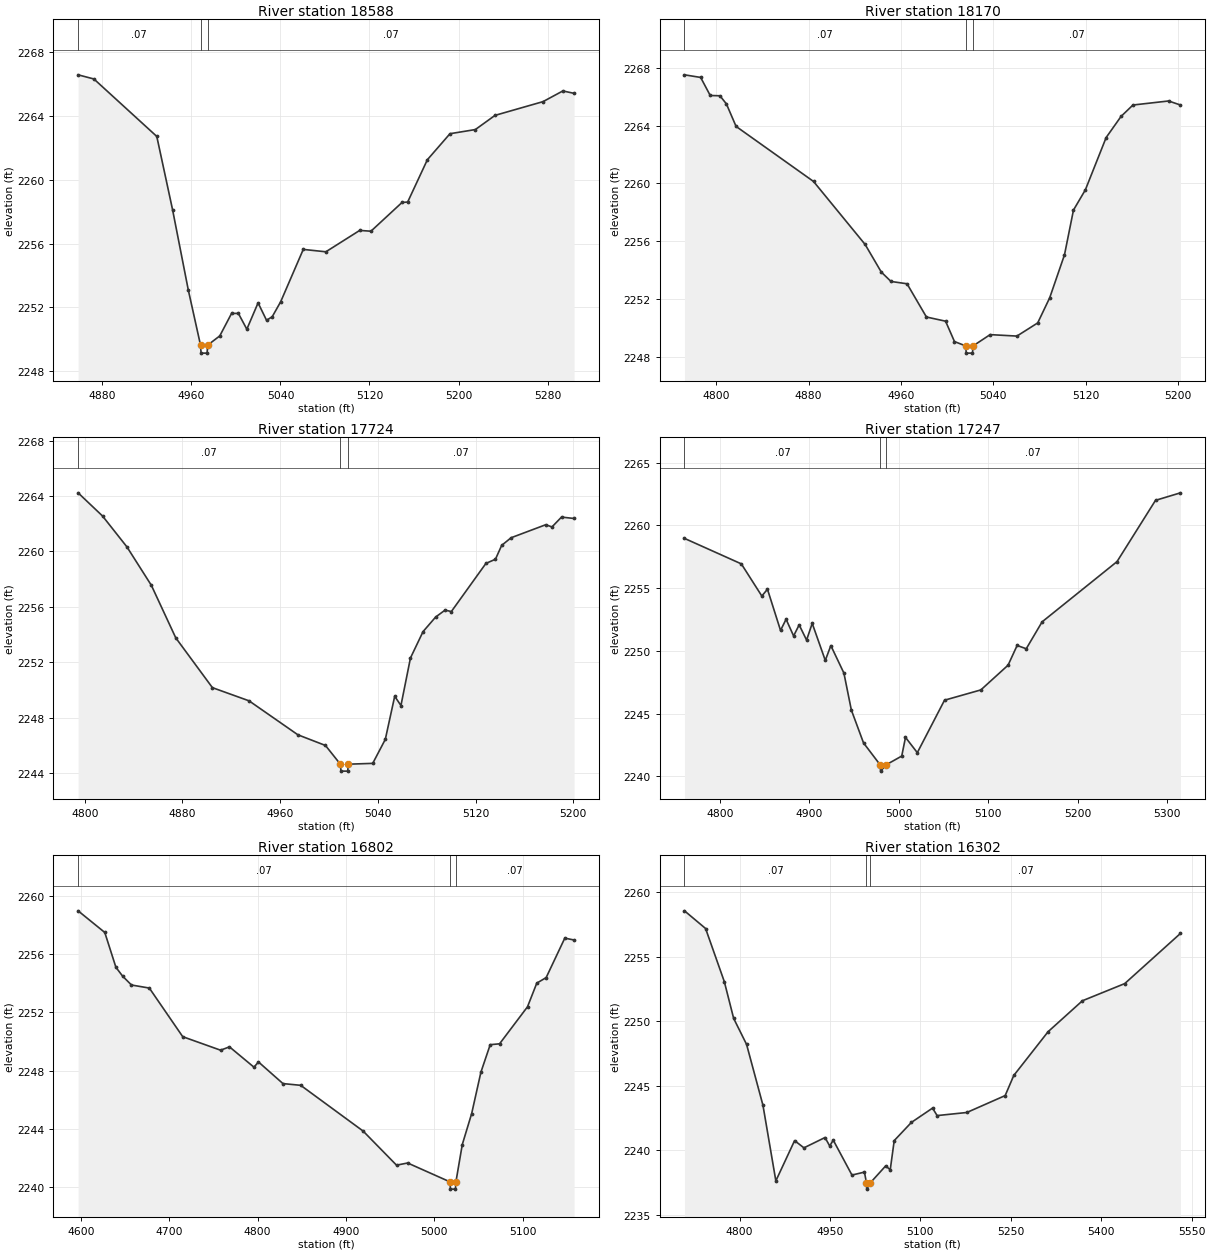
Type RM Length L Ch R = 1,18588,418,418,418
BEGIN DESCRIPTION:
Stream0112 39.0
END DESCRIPTION:
XS GIS Cut Line= 3
      1756874.98     13936825.02      1756975.00     13936725.00
      1757025.00     13936424.99
#Sta/Elev= 30
  4858.2 2266.58  4872.4 2266.32  4928.9 2262.72  4943.1 2258.12  4957.2 2253.10
  4968.2 2249.64  4968.7 2249.14  4974.1 2249.14  4974.6 2249.64  4985.5 2250.22
  4996.1 2251.63  5002.2 2251.63  5009.8 2250.64  5019.9 2252.29  5027.5 2251.20
  5032.6 2251.42  5040.2 2252.36  5060.5 2255.64  5080.8 2255.49  5111.2 2256.83
  5121.3 2256.78  5149.2 2258.58  5154.3 2258.61  5172.0 2261.26  5192.3 2262.89
  5215.1 2263.15  5232.8 2264.04  5275.9 2264.90  5293.7 2265.57  5303.8 2265.42
#Mann=3,-1,0
  4858.2    0.07       0  4968.2    0.05       0  4974.6    0.07       0
Bank Sta=4968.2,4974.6
Exp/Cntr=0.3,0.1

Type RM Length L Ch R = 1,18170,446,446,446
BEGIN DESCRIPTION:
Stream0112 38.0
END DESCRIPTION:
XS GIS Cut Line= 3
      1757225.01     13936974.98      1757325.00     13936775.00
      1757374.99     13936575.04
#Sta/Elev= 30
  4772.5 2267.52  4786.5 2267.34  4794.8 2266.09  4803.2 2266.07  4808.8 2265.51
  4817.2 2263.95  4884.3 2260.14  4929.0 2255.78  4943.0 2253.87  4951.4 2253.22
  4965.3 2253.06  4982.1 2250.76  4998.7 2250.47  5006.4 2249.06  5016.1 2248.76
  5016.6 2248.26  5022.0 2248.26  5022.5 2248.76  5037.3 2249.54  5060.5 2249.44
  5078.5 2250.35  5088.9 2252.09  5101.7 2255.06  5109.5 2258.16  5119.8 2259.56
  5137.8 2263.18  5150.7 2264.64  5161.0 2265.43  5191.9 2265.71  5202.2 2265.43
#Mann=3,-1,0
  4772.5    0.07       0  5016.1    0.05       0  5022.5    0.07       0
Bank Sta=5016.1,5022.5
Exp/Cntr=0.3,0.1

Type RM Length L Ch R = 1,17724,477,477,477
BEGIN DESCRIPTION:
Stream0112 37.0
END DESCRIPTION:
XS GIS Cut Line= 3
      1757725.00     13937025.02      1757725.00     13936825.00
      1757674.99     13936624.98
#Sta/Elev= 30
  4794.5 2264.23  4814.5 2262.56  4834.5 2260.33  4854.5 2257.56  4874.5 2253.77
  4904.5 2250.18  4934.5 2249.23  4974.5 2246.78  4997.1 2246.01  5009.3 2244.66
  5009.8 2244.16  5015.3 2244.16  5015.8 2244.66  5035.8 2244.72  5046.1 2246.45
  5053.8 2249.56  5058.9 2248.89  5066.7 2252.32  5077.0 2254.22  5087.3 2255.27
  5095.0 2255.77  5100.2 2255.67  5128.5 2259.14  5136.3 2259.44  5141.4 2260.44
  5149.1 2260.99  5177.5 2261.93  5182.6 2261.77  5190.4 2262.48  5200.7 2262.38
#Mann=3,-1,0
  4794.5    0.07       0  5009.3    0.05       0  5015.8    0.07       0
Bank Sta=5009.3,5015.8
Exp/Cntr=0.3,0.1

Type RM Length L Ch R = 1,17247,445,445,445
BEGIN DESCRIPTION:
Stream0112 36.0
END DESCRIPTION:
XS GIS Cut Line= 3
      1758025.01     13937024.99      1758175.00     13936825.00
      1758125.00     13936525.02
#Sta/Elev= 30
  4760.5 2258.96  4824.0 2256.93  4846.9 2254.37  4853.2 2254.91  4867.8 2251.63
  4874.0 2252.52  4882.4 2251.19  4888.6 2252.07  4896.9 2250.86  4903.2 2252.19
  4917.8 2249.24  4924.0 2250.42  4938.6 2248.23  4946.9 2245.29  4960.5 2242.67
  4979.1 2240.92  4979.6 2240.42  4985.7 2240.92  5003.2 2241.62  5007.4 2243.11
  5020.6 2241.89  5051.0 2246.07  5091.6 2246.89  5122.0 2248.86  5132.1 2250.43
  5142.3 2250.17  5160.0 2252.31  5243.7 2257.11  5286.7 2261.99  5314.6 2262.59
#Mann=3,-1,0
  4760.5    0.07       0  4979.1    0.05       0  4985.7    0.07       0
Bank Sta=4979.1,4985.7
Exp/Cntr=0.3,0.1

Type RM Length L Ch R = 1,16802,500,500,500
BEGIN DESCRIPTION:
Stream0112 35.0
END DESCRIPTION:
XS GIS Cut Line= 3
      1758525.00     13937124.97      1758575.00     13936725.00
      1758525.00     13936575.00
#Sta/Elev= 30
  4596.9 2259.00  4627.1 2257.51  4639.7 2255.11  4647.3 2254.50  4657.3 2253.89
  4677.5 2253.68  4715.3 2250.33  4758.1 2249.40  4768.2 2249.63  4795.9 2248.23
  4801.0 2248.59  4828.7 2247.10  4848.8 2246.98  4919.4 2243.83  4957.2 2241.48
  4969.8 2241.63  5017.7 2240.33  5018.2 2239.83  5023.9 2239.83  5024.4 2240.33
  5031.6 2242.90  5042.2 2245.03  5052.7 2247.89  5063.2 2249.78  5073.8 2249.84
  5105.4 2252.39  5115.9 2254.02  5126.5 2254.40  5147.6 2257.12  5158.1 2256.99
#Mann=3,-1,0
  4596.9    0.07       0  5017.7    0.05       0  5024.4    0.07       0
Bank Sta=5017.7,5024.4
Exp/Cntr=0.3,0.1

Type RM Length L Ch R = 1,16302,462,462,462
BEGIN DESCRIPTION:
Stream0112 34.0
END DESCRIPTION:
XS GIS Cut Line= 3
      1759224.99     13936974.98      1759075.00     13936725.00
      1758675.02     13936375.02
#Sta/Elev= 30
  4708.5 2258.54  4743.5 2257.17  4774.6 2253.05  4790.1 2250.20  4811.5 2248.19
  4838.7 2243.47  4860.1 2237.61  4891.2 2240.73  4906.7 2240.17  4941.7 2240.97
  4949.5 2240.31  4955.3 2240.77  4986.4 2238.06  5007.1 2238.29  5010.4 2237.47
  5010.9 2236.97  5017.1 2237.47  5042.3 2238.77  5049.9 2238.47  5056.5 2240.73
  5085.0 2242.14  5120.1 2243.25  5127.7 2242.67  5177.0 2242.91  5240.6 2244.22
  5254.9 2245.78  5311.8 2249.17  5368.8 2251.57  5439.0 2252.90  5531.5 2256.79
#Mann=3,-1,0
  4708.5    0.07       0  5010.4    0.05       0  5017.1    0.07       0
Bank Sta=5010.4,5017.1
Exp/Cntr=0.3,0.1

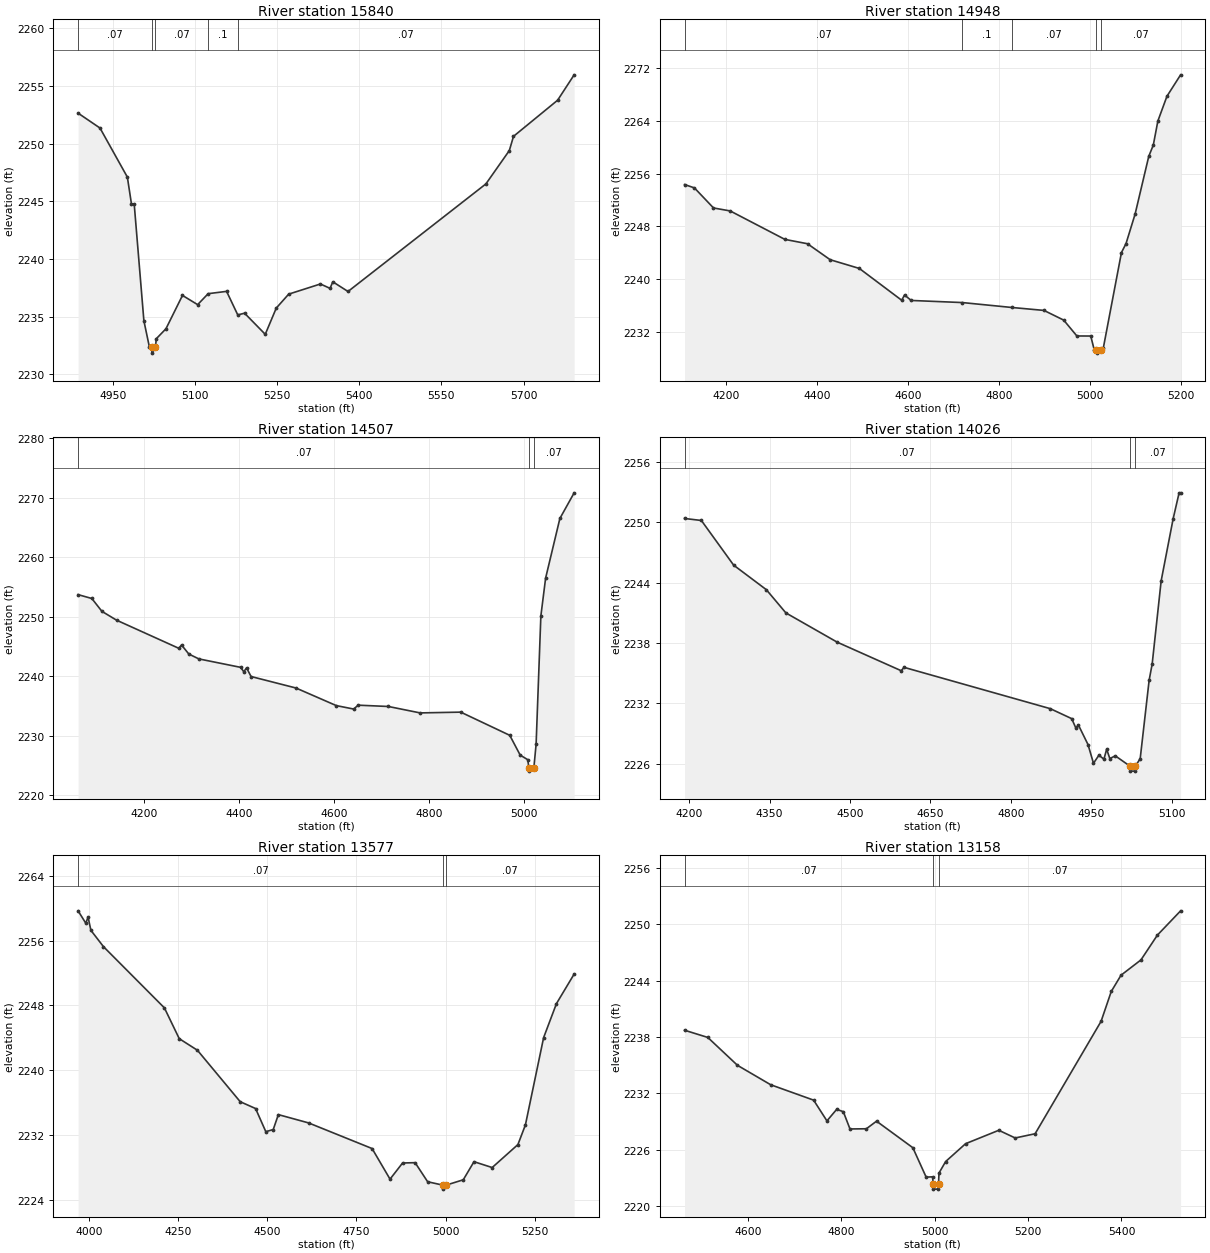
Type RM Length L Ch R = 1,15840,892,892,892
BEGIN DESCRIPTION:
Stream0112 33.0
END DESCRIPTION:
XS GIS Cut Line= 3
      1759475.00     13936675.02      1759475.00     13936575.00
      1759375.01     13935775.05
#Sta/Elev= 30
  4886.3 2252.63  4926.3 2251.34  4976.3 2247.09  4983.8 2244.76  4988.8 2244.76
  5006.5 2234.64  5016.6 2232.36  5020.7 2232.34  5021.2 2231.84  5027.5 2232.34
  5029.2 2233.09  5046.8 2233.95  5077.0 2236.84  5104.7 2236.04  5123.9 2236.99
  5157.6 2237.19  5178.0 2235.15  5190.4 2235.30  5228.2 2233.47  5248.3 2235.74
  5271.0 2236.95  5329.0 2237.83  5346.6 2237.45  5351.6 2238.02  5379.4 2237.18
  5631.3 2246.50  5674.1 2249.39  5681.7 2250.62  5762.3 2253.75  5792.5 2255.95
#Mann=5,-1,0
  4886.3    0.07       0  5020.7    0.05       0  5027.5    0.07       0
  5123.9     0.1       0  5178.0    0.07       0
Bank Sta=5020.7,5027.5
Exp/Cntr=0.3,0.1

Type RM Length L Ch R = 1,14948,441,441,441
BEGIN DESCRIPTION:
Stream0112 32.0
END DESCRIPTION:
XS GIS Cut Line= 3
      1759525.01     13936774.99      1760075.00     13936075.00
      1760075.00     13935875.01
#Sta/Elev= 30
  4109.4 2254.33  4131.1 2253.82  4173.0 2250.78  4209.7 2250.33  4329.9 2246.02
  4379.6 2245.36  4429.4 2242.94  4493.5 2241.62  4586.6 2236.80  4592.9 2237.60
  4607.4 2236.77  4719.9 2236.45  4828.0 2235.71  4899.3 2235.26  4942.7 2233.79
  4971.6 2231.39  5002.1 2231.38  5009.6 2229.33  5014.5 2229.29  5015.0 2228.79
  5024.8 2229.29  5029.6 2229.52  5069.6 2244.03  5079.6 2245.38  5099.6 2249.86
  5129.6 2258.60  5139.6 2260.31  5149.6 2263.95  5169.6 2267.71  5199.6 2270.95
#Mann=5,-1,0
  4109.4    0.07       0  4719.9     0.1       0  4828.0    0.07       0
  5014.5    0.05       0  5024.8    0.07       0
Bank Sta=5014.5,5024.8
Exp/Cntr=0.3,0.1

Type RM Length L Ch R = 1,14507,481,481,481
BEGIN DESCRIPTION:
Stream0112 31.0
END DESCRIPTION:
XS GIS Cut Line= 3
      1759574.98     13936825.01      1760375.00     13936325.00
      1760474.98     13936325.00
#Sta/Elev= 30
  4061.2 2253.73  4090.1 2253.08  4111.3 2250.92  4142.0 2249.44  4272.9 2244.71
  4278.8 2245.26  4294.1 2243.74  4315.3 2242.92  4403.2 2241.50  4409.7 2240.76
  4415.6 2241.41  4425.0 2239.96  4519.4 2238.03  4604.3 2235.07  4640.8 2234.49
  4650.3 2235.14  4713.9 2234.92  4780.6 2233.84  4866.1 2233.97  4969.2 2230.07
  4991.1 2226.74  5007.1 2225.97  5009.4 2224.55  5009.9 2224.05  5019.8 2224.55
  5024.6 2228.58  5034.6 2250.15  5044.6 2256.51  5074.6 2266.54  5104.6 2270.85
#Mann=3,-1,0
  4061.2    0.07       0  5009.4    0.05       0  5019.8    0.07       0
Bank Sta=5009.4,5019.8
Exp/Cntr=0.3,0.1

Type RM Length L Ch R = 1,14026,449,449,449
BEGIN DESCRIPTION:
Stream0112 30.0
END DESCRIPTION:
XS GIS Cut Line= 3
      1759675.00     13936925.00      1760475.00     13936775.00
      1760574.96     13936725.02
#Sta/Elev= 30
  4191.2 2250.39  4222.6 2250.19  4282.8 2245.75  4343.8 2243.31  4380.3 2241.00
  4476.1 2238.09  4595.6 2235.25  4600.7 2235.59  4873.7 2231.48  4913.6 2230.49
  4921.2 2229.58  4926.3 2229.84  4944.1 2227.91  4954.3 2226.05  4964.4 2226.85
  4973.8 2226.46  4978.9 2227.45  4984.8 2226.52  4995.0 2226.79  5022.3 2225.77
  5022.8 2225.27  5032.2 2225.27  5032.7 2225.77  5041.5 2226.52  5058.2 2234.32
  5063.8 2235.91  5080.6 2244.19  5103.0 2250.37  5114.1 2252.94  5116.9 2252.94
#Mann=3,-1,0
  4191.2    0.07       0  5022.3    0.05       0  5032.7    0.07       0
Bank Sta=5022.3,5032.7
Exp/Cntr=0.3,0.1

Type RM Length L Ch R = 1,13577,419,419,419
BEGIN DESCRIPTION:
Stream0112 29.0
END DESCRIPTION:
XS GIS Cut Line= 3
      1759875.02     13937974.98      1760525.00     13937175.00
      1760725.00     13936875.00
#Sta/Elev= 30
  3969.3 2259.66  3990.8 2258.14  3997.3 2258.88  4005.2 2257.26  4040.4 2255.25
  4211.4 2247.70  4253.0 2243.91  4304.0 2242.48  4424.0 2236.14  4467.1 2235.30
  4495.8 2232.45  4516.6 2232.71  4531.0 2234.55  4615.7 2233.53  4793.9 2230.37
  4844.2 2226.60  4879.4 2228.59  4914.6 2228.63  4949.7 2226.28  4991.6 2225.87
  4992.1 2225.37  5002.0 2225.87  5049.6 2226.52  5079.7 2228.75  5130.7 2228.03
  5202.9 2230.86  5223.9 2233.28  5275.0 2244.04  5311.0 2248.23  5360.6 2251.87
#Mann=3,-1,0
  3969.3    0.07       0  4991.6    0.05       0  5002.0    0.07       0
Bank Sta=4991.6,5002
Exp/Cntr=0.3,0.1

Type RM Length L Ch R = 1,13158,418,418,418
BEGIN DESCRIPTION:
Stream0112 28.0
END DESCRIPTION:
XS GIS Cut Line= 3
      1760375.02     13937924.97      1760725.00     13937525.00
      1761125.02     13937174.99
#Sta/Elev= 30
  4463.7 2238.72  4513.5 2237.95  4577.1 2234.98  4648.3 2232.91  4740.3 2231.27
  4768.8 2229.06  4789.7 2230.29  4803.9 2230.04  4818.2 2228.20  4853.3 2228.22
  4875.1 2229.03  4952.9 2226.20  4981.4 2223.07  4995.2 2223.10  4996.6 2222.29
  4997.1 2221.79  5007.4 2221.79  5007.9 2222.29  5008.9 2223.50  5023.2 2224.73
  5065.9 2226.63  5137.1 2228.06  5172.2 2227.24  5214.9 2227.69  5356.3 2239.67
  5378.1 2242.85  5399.0 2244.58  5441.7 2246.21  5476.9 2248.85  5526.7 2251.44
#Mann=3,-1,0
  4463.7    0.07       0  4996.6    0.05       0  5007.9    0.07       0
Bank Sta=4996.6,5007.9
Exp/Cntr=0.3,0.1

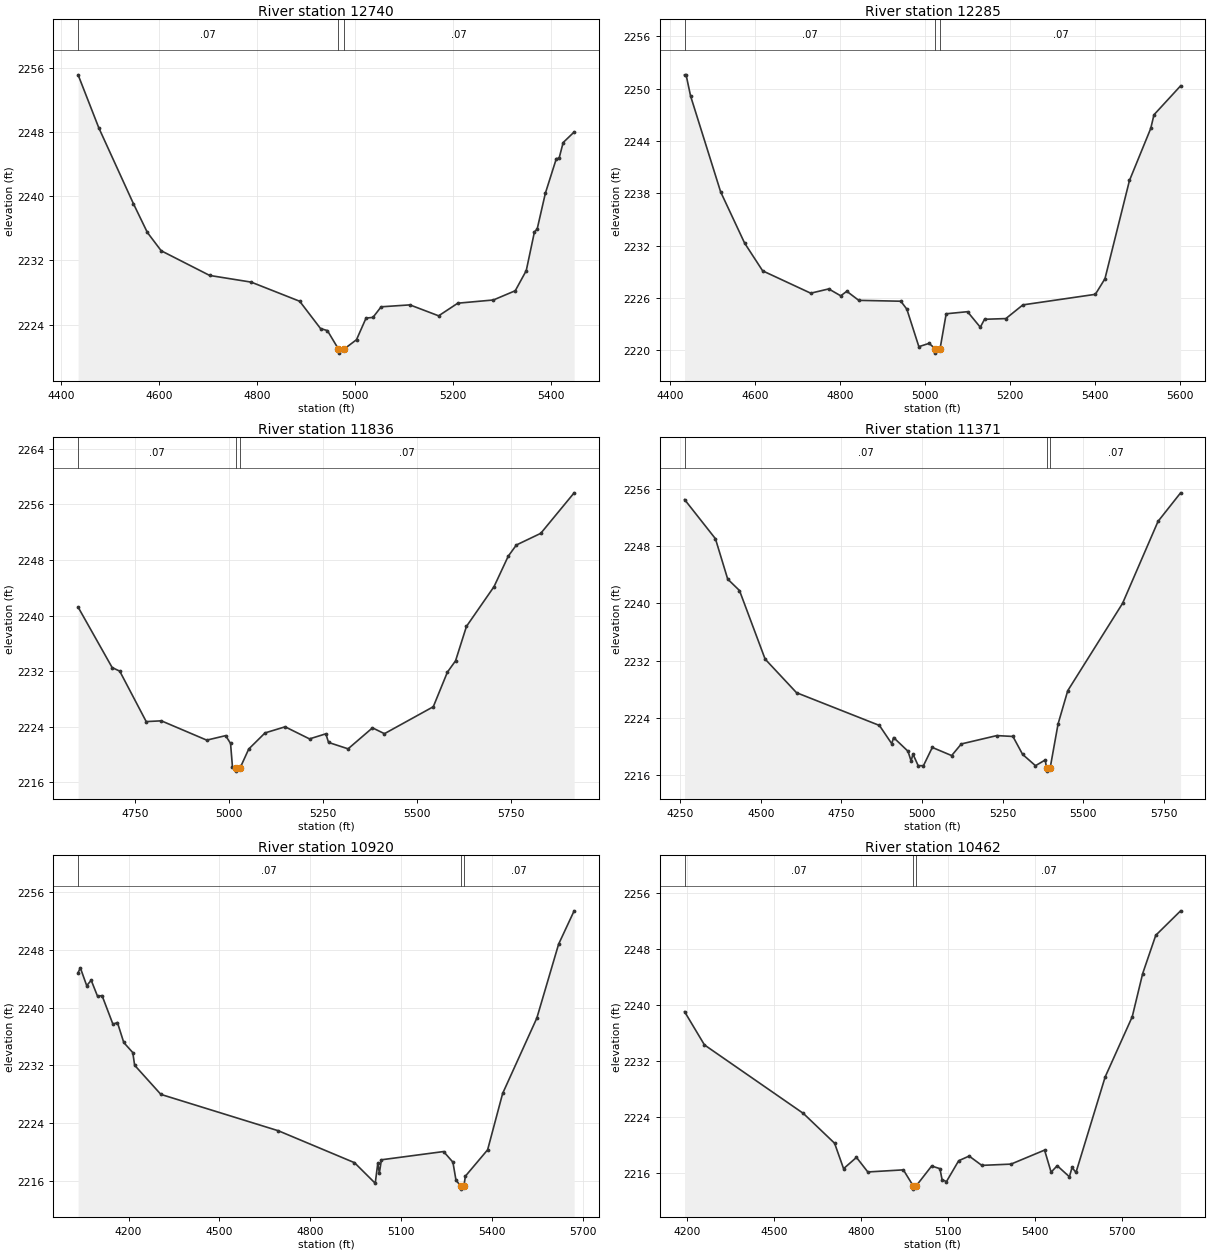
Type RM Length L Ch R = 1,12740,455,455,455
BEGIN DESCRIPTION:
Stream0112 27.0
END DESCRIPTION:
XS GIS Cut Line= 3
      1760625.01     13938174.99      1761025.00     13937775.00
      1761225.00     13937374.99
#Sta/Elev= 30
  4434.1 2255.09  4476.5 2248.48  4547.2 2239.05  4575.5 2235.49  4603.8 2233.21
  4702.8 2230.14  4787.6 2229.31  4886.6 2226.93  4929.1 2223.54  4943.2 2223.28
  4965.8 2220.98  4966.3 2220.48  4977.2 2220.98  5002.6 2222.15  5022.1 2224.84
  5036.1 2224.92  5052.9 2226.24  5111.6 2226.48  5170.3 2225.12  5209.4 2226.69
  5282.1 2227.09  5326.8 2228.24  5349.2 2230.74  5365.9 2235.55  5371.5 2235.91
  5388.3 2240.38  5410.7 2244.68  5416.2 2244.70  5424.6 2246.67  5447.0 2247.98
#Mann=3,-1,0
  4434.1    0.07       0  4965.8    0.05       0  4977.2    0.07       0
Bank Sta=4965.8,4977.2
Exp/Cntr=0.3,0.1

Type RM Length L Ch R = 1,12285,449,449,449
BEGIN DESCRIPTION:
Stream0112 26.0
END DESCRIPTION:
XS GIS Cut Line= 3
      1761024.99     13938325.01      1761425.00     13937925.00
      1761375.00     13937324.98
#Sta/Elev= 30
  4433.9 2251.59  4437.5 2251.59  4448.1 2249.16  4518.8 2238.18  4575.3 2232.30
  4617.8 2229.12  4730.9 2226.56  4773.3 2227.05  4801.6 2226.26  4815.8 2226.78
  4844.0 2225.74  4943.0 2225.64  4957.2 2224.73  4985.5 2220.43  5009.6 2220.81
  5024.0 2220.19  5024.5 2219.69  5035.4 2220.19  5049.8 2224.20  5100.0 2224.44
  5130.1 2222.66  5140.1 2223.57  5190.3 2223.65  5230.4 2225.22  5401.0 2226.43
  5423.6 2228.22  5481.3 2239.48  5531.4 2245.45  5539.0 2247.01  5601.7 2250.33
#Mann=3,-1,0
  4433.9    0.07       0  5024.0    0.05       0  5035.4    0.07       0
Bank Sta=5024,5035.4
Exp/Cntr=0.3,0.1

Type RM Length L Ch R = 1,11836,465,465,465
BEGIN DESCRIPTION:
Stream0112 25.0
END DESCRIPTION:
XS GIS Cut Line= 3
      1761875.00     13938375.00      1761825.00     13937975.00
      1761374.99     13937174.99
#Sta/Elev= 30
  4597.2 2241.22  4687.9 2232.52  4708.1 2232.00  4778.6 2224.74  4818.9 2224.85
  4939.8 2222.07  4990.2 2222.72  5003.2 2221.59  5008.3 2218.21  5017.5 2218.11
  5018.0 2217.61  5029.0 2218.11  5051.6 2220.79  5095.0 2223.11  5148.5 2223.99
  5213.5 2222.25  5256.9 2222.98  5264.2 2221.74  5316.2 2220.82  5381.2 2223.84
  5413.0 2223.00  5543.1 2226.88  5580.7 2231.86  5602.4 2233.49  5631.4 2238.44
  5705.0 2244.18  5742.6 2248.54  5764.3 2250.16  5829.3 2251.84  5918.2 2257.67
#Mann=3,-1,0
  4597.2    0.07       0  5017.5    0.05       0  5029.0    0.07       0
Bank Sta=5017.5,5029
Exp/Cntr=0.3,0.1

Type RM Length L Ch R = 1,11371,451,451,451
BEGIN DESCRIPTION:
Stream0112 24.0
END DESCRIPTION:
XS GIS Cut Line= 3
      1761875.02     13938524.96      1762225.00     13937875.00
      1762225.00     13937075.00
#Sta/Elev= 30
  4263.4 2254.56  4359.1 2249.07  4397.2 2243.41  4433.7 2241.81  4513.2 2232.20
  4610.6 2227.49  4867.7 2222.90  4905.9 2220.34  4911.5 2221.21  4956.2 2219.29
  4965.9 2217.92  4971.6 2218.89  4987.8 2217.27  5004.1 2217.26  5031.6 2219.82
  5091.6 2218.68  5121.6 2220.31  5231.6 2221.48  5281.6 2221.36  5311.6 2218.85
  5351.6 2217.26  5381.6 2218.06  5385.8 2217.00  5386.3 2216.50  5397.3 2217.00
  5421.6 2223.11  5451.6 2227.77  5621.6 2240.01  5731.6 2251.50  5801.6 2255.50
#Mann=3,-1,0
  4263.4    0.07       0  5385.8    0.05       0  5397.3    0.07       0
Bank Sta=5385.8,5397.3
Exp/Cntr=0.3,0.1

Type RM Length L Ch R = 1,10920,458,458,458
BEGIN DESCRIPTION:
Stream0112 23.0
END DESCRIPTION:
XS GIS Cut Line= 3
      1762025.02     13938574.97      1762575.00     13937775.00
      1762424.99     13937124.98
#Sta/Elev= 30
  4033.2 2244.82  4040.6 2245.50  4061.6 2243.03  4076.5 2243.77  4097.4 2241.56
  4112.3 2241.65  4148.2 2237.70  4163.1 2237.92  4184.0 2235.16  4213.8 2233.76
  4219.9 2232.01  4306.5 2227.98  4694.8 2222.94  4945.8 2218.53  5014.3 2215.68
  5022.8 2218.45  5027.9 2217.10  5034.8 2218.93  5240.0 2220.07  5270.8 2218.60
  5281.1 2216.07  5295.9 2215.37  5296.4 2214.87  5307.4 2215.37  5311.9 2216.66
  5385.4 2220.31  5435.0 2228.11  5547.9 2238.54  5619.8 2248.77  5671.1 2253.38
#Mann=3,-1,0
  4033.2    0.07       0  5295.9    0.05       0  5307.4    0.07       0
Bank Sta=5295.9,5307.4
Exp/Cntr=0.3,0.1

Type RM Length L Ch R = 1,10462,435,435,435
BEGIN DESCRIPTION:
Stream0112 22.0
END DESCRIPTION:
XS GIS Cut Line= 3
      1763274.98     13938574.95      1762975.00     13937825.00
      1762475.01     13937075.01
#Sta/Elev= 30
  4192.3 2239.03  4260.9 2234.28  4601.5 2224.51  4709.2 2220.25  4740.2 2216.62
  4784.6 2218.23  4823.7 2216.15  4946.2 2216.45  4979.5 2214.20  4980.0 2213.70
  4991.0 2214.20  5043.6 2217.00  5072.1 2216.62  5079.6 2215.05  5094.7 2214.78
  5136.7 2217.75  5172.8 2218.42  5216.4 2217.09  5317.0 2217.27  5432.7 2219.27
  5455.2 2216.12  5476.3 2217.04  5518.3 2215.46  5527.3 2216.79  5540.9 2216.08
  5641.5 2229.72  5734.7 2238.30  5770.7 2244.47  5815.8 2249.93  5901.4 2253.42
#Mann=3,-1,0
  4192.3    0.07       0  4979.5    0.05       0  4991.0    0.07       0
Bank Sta=4979.5,4991
Exp/Cntr=0.3,0.1

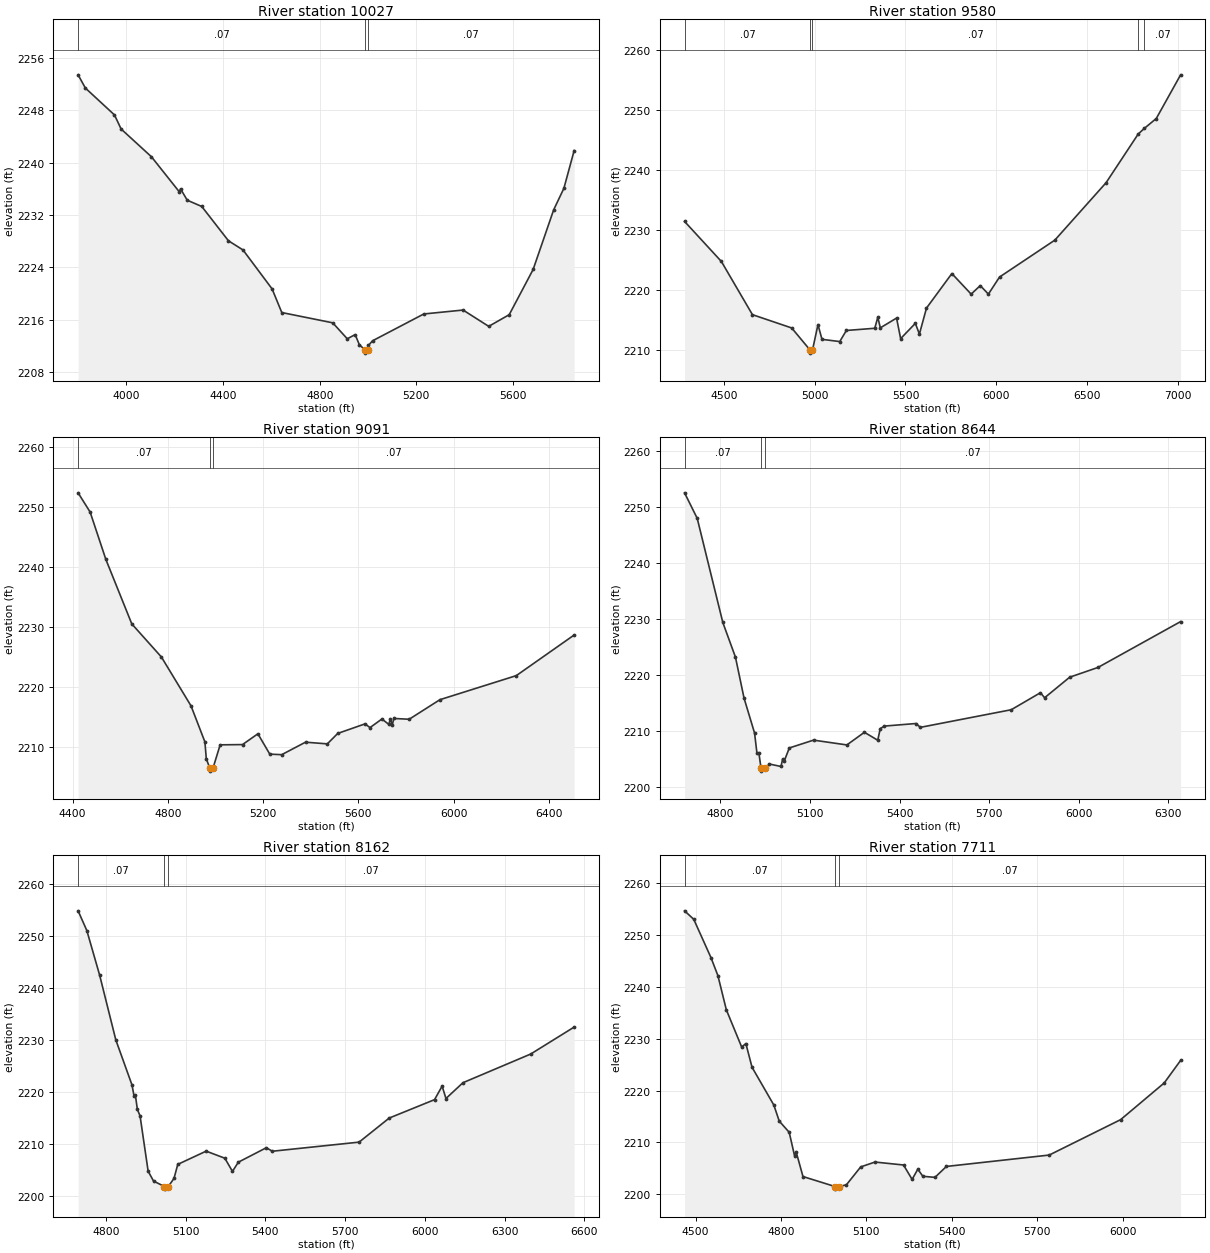
Type RM Length L Ch R = 1,10027,447,447,447
BEGIN DESCRIPTION:
Stream0112 21.0
END DESCRIPTION:
XS GIS Cut Line= 3
      1763275.00     13938925.03      1763375.00     13937725.00
      1762775.01     13937125.01
#Sta/Elev= 30
  3800.2 2253.40  3830.3 2251.38  3950.8 2247.27  3978.3 2245.12  4103.8 2240.88
  4219.2 2235.52  4224.2 2235.98  4251.8 2234.25  4312.0 2233.29  4422.4 2228.05
  4482.6 2226.65  4603.0 2220.70  4643.1 2217.09  4853.9 2215.52  4914.1 2213.08
  4946.7 2213.72  4964.3 2212.15  4987.9 2211.39  4988.4 2210.89  5000.9 2211.39
  5001.9 2212.07  5018.5 2212.77  5230.7 2216.87  5393.3 2217.47  5499.4 2214.98
  5584.2 2216.76  5683.2 2223.67  5768.1 2232.77  5810.5 2236.07  5852.9 2241.83
#Mann=3,-1,0
  3800.2    0.07       0  4987.9    0.05       0  5000.9    0.07       0
Bank Sta=4987.9,5000.9
Exp/Cntr=0.3,0.1

Type RM Length L Ch R = 1,9580,489,489,489
BEGIN DESCRIPTION:
Stream0112 20.0
END DESCRIPTION:
XS GIS Cut Line= 3
      1763375.02     13938374.97      1763775.00     13937775.00
      1762875.02     13935975.03
#Sta/Elev= 30
  4282.8 2231.44  4485.6 2224.76  4656.8 2215.88  4873.2 2213.66  4974.8 2209.96
  4975.3 2209.46  4987.8 2209.96  5017.9 2214.22  5040.2 2211.76  5138.0 2211.39
  5174.4 2213.24  5330.9 2213.61  5347.7 2215.44  5361.6 2213.68  5451.1 2215.31
  5473.5 2211.88  5554.5 2214.43  5576.9 2212.64  5616.0 2216.98  5755.8 2222.74
  5862.0 2219.31  5912.3 2220.73  5957.0 2219.31  6018.5 2222.16  6323.2 2228.32
  6605.5 2237.90  6782.4 2246.02  6816.0 2246.96  6882.2 2248.62  7016.3 2255.91
#Mann=5,-1,0
  4282.8    0.07       0  4974.8    0.05       0  4987.8    0.07       0
  6782.4     0.1       0  6816.0    0.07       0
Bank Sta=4974.8,4987.8
Exp/Cntr=0.3,0.1

Type RM Length L Ch R = 1,9091,447,447,447
BEGIN DESCRIPTION:
Stream0112 19.0
END DESCRIPTION:
XS GIS Cut Line= 3
      1764724.99     13938074.99      1764225.00     13937775.00
      1763324.99     13936574.99
#Sta/Elev= 30
  4422.9 2252.39  4473.4 2249.19  4539.5 2241.30  4648.4 2230.56  4772.7 2225.05
  4897.1 2216.91  4955.4 2210.91  4961.3 2208.09  4976.0 2206.54  4976.5 2206.04
  4989.4 2206.54  5019.5 2210.42  5113.3 2210.46  5177.9 2212.26  5227.9 2208.87
  5277.9 2208.78  5377.9 2210.86  5469.5 2210.58  5513.3 2212.32  5627.9 2213.91
  5648.7 2213.29  5698.7 2214.72  5727.9 2213.82  5734.1 2214.74  5742.4 2213.72
  5748.7 2214.81  5813.3 2214.68  5942.4 2217.94  6263.3 2221.95  6506.0 2228.71
#Mann=3,-1,0
  4422.9    0.07       0  4976.0    0.05       0  4989.4    0.07       0
Bank Sta=4976,4989.4
Exp/Cntr=0.3,0.1

Type RM Length L Ch R = 1,8644,482,482,482
BEGIN DESCRIPTION:
Stream0112 18.0
END DESCRIPTION:
XS GIS Cut Line= 3
      1764825.01     13937875.01      1764625.00     13937625.00
      1764025.00     13936425.01
#Sta/Elev= 30
  4679.8 2252.58  4722.2 2248.02  4807.9 2229.42  4850.3 2223.22  4879.1 2215.89
  4914.3 2209.66  4922.3 2206.05  4928.7 2206.14  4936.0 2203.35  4936.5 2202.85
  4950.3 2203.35  4963.9 2204.12  5002.8 2203.68  5008.4 2205.01  5013.9 2204.67
  5030.7 2206.99  5111.8 2208.39  5223.6 2207.53  5282.3 2209.79  5327.0 2208.37
  5335.4 2210.45  5349.4 2210.90  5455.6 2211.36  5469.5 2210.67  5774.2 2213.82
  5872.0 2216.86  5886.0 2215.96  5969.9 2219.63  6064.9 2221.38  6341.6 2229.57
#Mann=3,-1,0
  4679.8    0.07       0  4936.0    0.05       0  4950.3    0.07       0
Bank Sta=4936,4950.3
Exp/Cntr=0.3,0.1

Type RM Length L Ch R = 1,8162,451,451,451
BEGIN DESCRIPTION:
Stream0112 17.0
END DESCRIPTION:
XS GIS Cut Line= 3
      1765124.99     13937824.96      1765075.00     13937525.00
      1764075.03     13936325.04
#Sta/Elev= 30
  4695.9 2254.81  4728.8 2251.02  4777.0 2242.46  4837.8 2230.04  4898.6 2221.40
  4906.2 2219.33  4911.3 2219.48  4918.9 2216.69  4929.0 2215.46  4959.4 2204.84
  4979.7 2202.95  5020.8 2201.90  5021.3 2201.40  5035.1 2201.90  5056.6 2203.44
  5070.9 2206.15  5177.7 2208.69  5248.0 2207.33  5276.6 2204.80  5298.7 2206.57
  5404.2 2209.35  5426.3 2208.67  5753.0 2210.42  5866.3 2215.04  6036.8 2218.57
  6065.4 2221.17  6079.8 2218.79  6143.6 2221.82  6398.7 2227.33  6562.0 2232.50
#Mann=3,-1,0
  4695.9    0.07       0  5020.8    0.05       0  5035.1    0.07       0
Bank Sta=5020.8,5035.1
Exp/Cntr=0.3,0.1

Type RM Length L Ch R = 1,7711,468,468,468
BEGIN DESCRIPTION:
Stream0112 16.0
END DESCRIPTION:
XS GIS Cut Line= 3
      1765274.99     13937875.02      1765475.00     13937375.00
      1765375.00     13936175.00
#Sta/Elev= 30
  4461.4 2254.71  4493.7 2253.07  4554.3 2245.66  4578.5 2242.20  4608.2 2235.59
  4662.0 2228.41  4676.8 2229.07  4698.4 2224.50  4775.1 2217.19  4794.0 2214.10
  4829.0 2211.94  4847.8 2207.41  4853.2 2208.20  4877.4 2203.39  4990.1 2201.46
  4990.6 2200.96  5004.4 2201.46  5030.0 2201.80  5080.2 2205.25  5130.4 2206.19
  5230.7 2205.62  5260.8 2202.84  5280.9 2204.81  5298.5 2203.44  5341.1 2203.23
  5381.3 2205.34  5742.5 2207.54  5993.4 2214.38  6146.4 2221.46  6204.1 2225.82
#Mann=3,-1,0
  4461.4    0.07       0  4990.1    0.05       0  5004.4    0.07       0
Bank Sta=4990.1,5004.4
Exp/Cntr=0.3,0.1