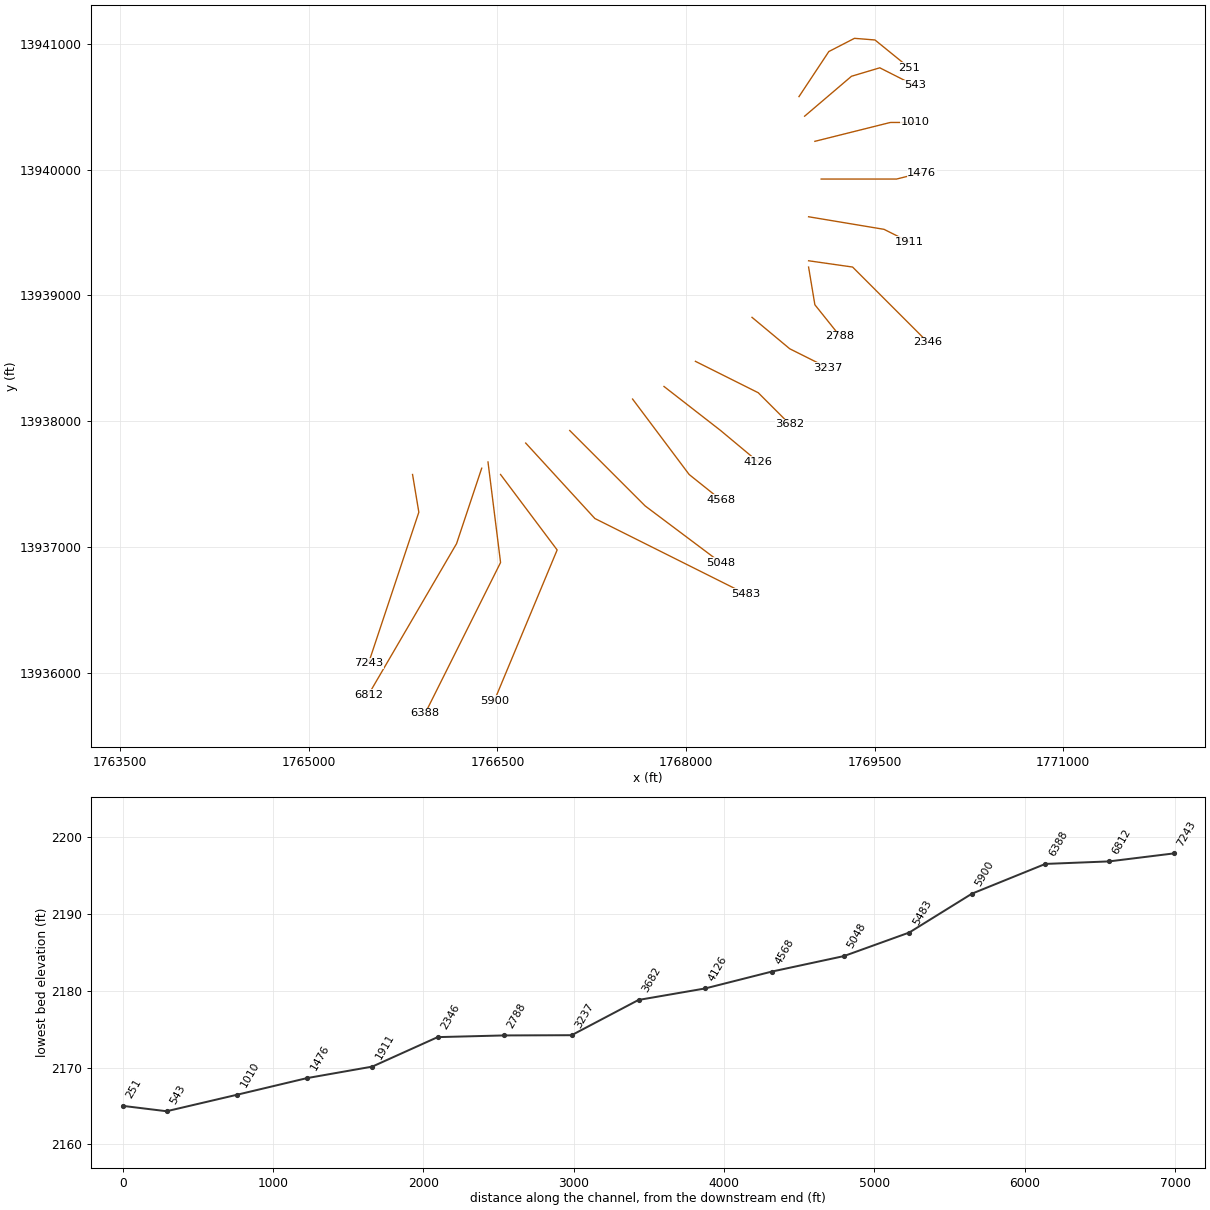
HEC-RAS study Stream0112.prj: Stream0112 Base Level Engineering

--- Stream0112.g01 (geometry) --- (continued)

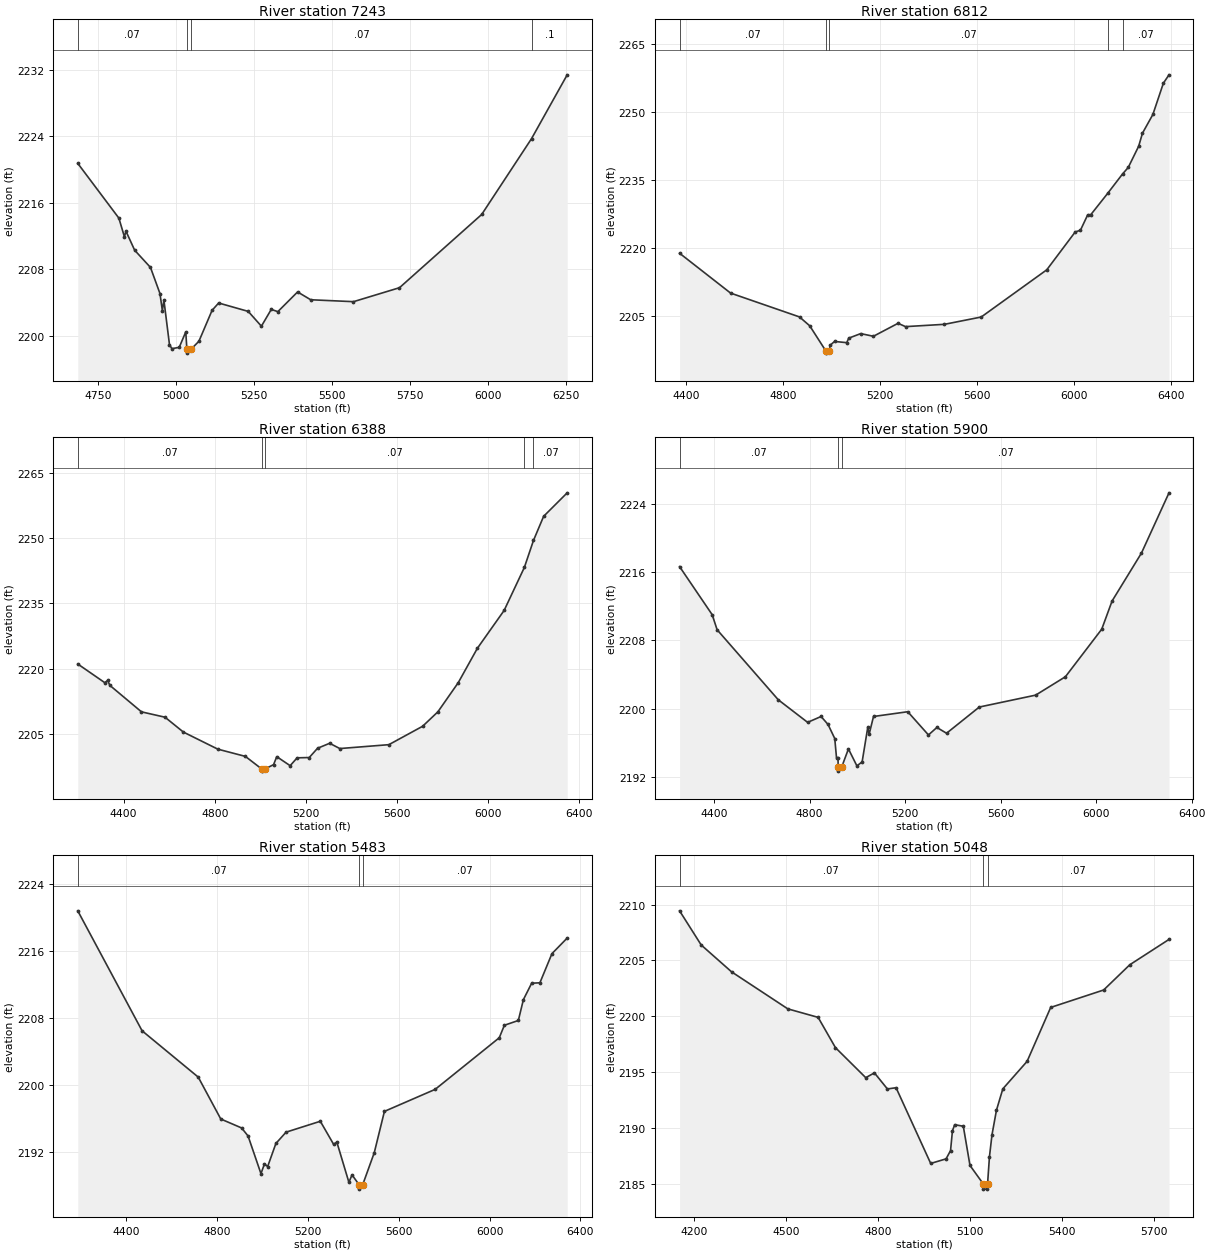
Type RM Length L Ch R = 1,7243,431,431,431
BEGIN DESCRIPTION:
Stream0112 15.0
END DESCRIPTION:
XS GIS Cut Line= 3
      1765825.01     13937574.96      1765875.00     13937275.00
      1765475.00     13936075.01
#Sta/Elev= 30
  4685.8 2220.72  4817.6 2214.13  4835.3 2211.89  4840.4 2212.55  4868.2 2210.27
  4918.9 2208.20  4949.3 2205.06  4957.0 2203.00  4962.0 2204.25  4979.8 2198.92
  4987.4 2198.43  5011.0 2198.58  5032.1 2200.45  5035.5 2198.39  5036.0 2197.89
  5049.8 2198.39  5074.2 2199.32  5116.4 2203.04  5137.5 2203.92  5232.3 2202.91
  5274.5 2201.13  5306.1 2203.15  5327.2 2202.88  5390.5 2205.25  5432.6 2204.31
  5569.7 2204.08  5717.2 2205.76  5980.7 2214.57  6140.6 2223.70  6254.8 2231.37
#Mann=4,-1,0
  4685.8    0.07       0  5035.5    0.05       0  5049.8    0.07       0
  6140.6     0.1       0
Bank Sta=5035.5,5049.8
Exp/Cntr=0.3,0.1

Type RM Length L Ch R = 1,6812,424,424,424
BEGIN DESCRIPTION:
Stream0112 14.0
END DESCRIPTION:
XS GIS Cut Line= 3
      1766374.99     13937624.98      1766175.00     13937025.00
      1765474.99     13935824.98
#Sta/Elev= 30
  4372.1 2218.90  4582.9 2210.10  4867.5 2204.84  4909.7 2202.88  4976.1 2197.35
  4976.6 2196.85  4990.9 2197.35  4994.0 2198.59  5012.4 2199.43  5062.4 2199.16
  5071.1 2200.16  5120.3 2201.16  5172.8 2200.57  5274.5 2203.43  5305.5 2202.70
  5466.4 2203.21  5618.1 2204.82  5888.9 2215.24  6006.4 2223.60  6027.9 2223.97
  6058.0 2227.38  6070.9 2227.42  6140.1 2232.09  6201.8 2236.39  6225.5 2237.84
  6268.5 2242.52  6284.2 2245.40  6327.2 2249.53  6370.6 2256.44  6393.8 2258.28
#Mann=5,-1,0
  4372.1    0.07       0  4976.1    0.05       0  4990.9    0.07       0
  6140.1     0.1       0  6201.8    0.07       0
Bank Sta=4976.1,4990.9
Exp/Cntr=0.3,0.1

Type RM Length L Ch R = 1,6388,488,488,488
BEGIN DESCRIPTION:
Stream0112 13.0
END DESCRIPTION:
XS GIS Cut Line= 3
      1766425.01     13937674.96      1766525.00     13936875.00
      1765925.01     13935675.02
#Sta/Elev= 30
  4198.6 2221.10  4317.0 2216.82  4329.6 2217.32  4339.6 2216.19  4478.2 2210.12
  4581.5 2208.89  4662.1 2205.48  4813.3 2201.56  4934.2 2199.90  5005.7 2197.02
  5006.2 2196.52  5020.6 2197.02  5057.9 2198.01  5071.9 2199.84  5130.6 2197.77
  5161.3 2199.57  5214.4 2199.64  5250.8 2201.76  5303.9 2202.91  5348.6 2201.70
  5563.8 2202.59  5711.9 2206.81  5779.0 2210.13  5868.5 2216.83  5952.3 2224.71
  6069.7 2233.39  6158.4 2243.25  6198.4 2249.44  6243.0 2254.98  6346.4 2260.37
#Mann=5,-1,0
  4198.6    0.07       0  5005.7    0.05       0  5020.6    0.07       0
  6158.4     0.1       0  6198.4    0.07       0
Bank Sta=5005.7,5020.6
Exp/Cntr=0.3,0.1

Type RM Length L Ch R = 1,5900,417,417,417
BEGIN DESCRIPTION:
Stream0112 12.0
END DESCRIPTION:
XS GIS Cut Line= 3
      1766525.01     13937574.98      1766975.00     13936975.00
      1766474.99     13935774.98
#Sta/Elev= 30
  4255.1 2216.68  4391.5 2211.04  4412.4 2209.26  4668.6 2201.03  4791.5 2198.38
  4847.8 2199.07  4877.0 2198.13  4905.1 2196.48  4912.4 2194.23  4918.6 2194.18
  4919.5 2193.15  4920.0 2192.65  4934.4 2193.15  4962.4 2195.26  4997.8 2193.27
  5019.7 2193.73  5043.5 2197.82  5049.0 2196.97  5067.4 2199.07  5210.9 2199.63
  5297.6 2196.90  5332.8 2197.78  5373.4 2197.10  5510.5 2200.18  5746.6 2201.58
  5871.2 2203.74  6023.4 2209.33  6066.7 2212.64  6189.7 2218.27  6305.1 2225.35
#Mann=3,-1,0
  4255.1    0.07       0  4919.5    0.05       0  4934.4    0.07       0
Bank Sta=4919.5,4934.4
Exp/Cntr=0.3,0.1

Type RM Length L Ch R = 1,5483,435,435,435
BEGIN DESCRIPTION:
Stream0112 11.0
END DESCRIPTION:
XS GIS Cut Line= 3
      1766725.00     13937825.00      1767275.00     13937225.00
      1768475.02     13936624.99
#Sta/Elev= 30
  4186.3 2220.81  4469.6 2206.49  4716.9 2200.96  4816.2 2195.96  4908.1 2194.89
  4936.4 2193.93  4993.1 2189.44  5008.6 2190.60  5022.6 2190.28  5058.9 2193.04
  5103.7 2194.39  5254.6 2195.69  5313.3 2192.93  5327.3 2193.21  5380.4 2188.41
  5394.3 2189.29  5426.0 2188.09  5426.5 2187.59  5440.9 2188.09  5492.2 2191.94
  5536.9 2196.87  5760.5 2199.50  6042.8 2205.66  6065.2 2207.15  6126.7 2207.72
  6149.0 2210.21  6185.4 2212.17  6221.7 2212.22  6274.8 2215.70  6341.9 2217.56
#Mann=3,-1,0
  4186.3    0.07       0  5426.0    0.05       0  5440.9    0.07       0
Bank Sta=5426,5440.9
Exp/Cntr=0.3,0.1

Type RM Length L Ch R = 1,5048,480,480,480
BEGIN DESCRIPTION:
Stream0112 10.0
END DESCRIPTION:
XS GIS Cut Line= 3
      1767075.00     13937925.00      1767675.00     13937325.00
      1768274.98     13936875.02
#Sta/Elev= 30
  4151.5 2209.44  4222.2 2206.38  4321.2 2203.98  4505.1 2200.66  4604.0 2199.90
  4660.6 2197.19  4759.6 2194.50  4787.9 2194.93  4830.3 2193.49  4858.6 2193.60
  4971.7 2186.82  5021.9 2187.23  5036.5 2187.97  5042.7 2189.74  5050.0 2190.29
  5078.2 2190.15  5100.0 2186.64  5142.5 2185.02  5143.0 2184.52  5157.0 2184.52
  5157.5 2185.02  5163.6 2187.42  5171.9 2189.39  5186.5 2191.59  5207.3 2193.50
  5286.5 2195.96  5363.6 2200.79  5536.5 2202.35  5621.9 2204.61  5750.0 2206.88
#Mann=3,-1,0
  4151.5    0.07       0  5142.5    0.05       0  5157.5    0.07       0
Bank Sta=5142.5,5157.5
Exp/Cntr=0.3,0.1

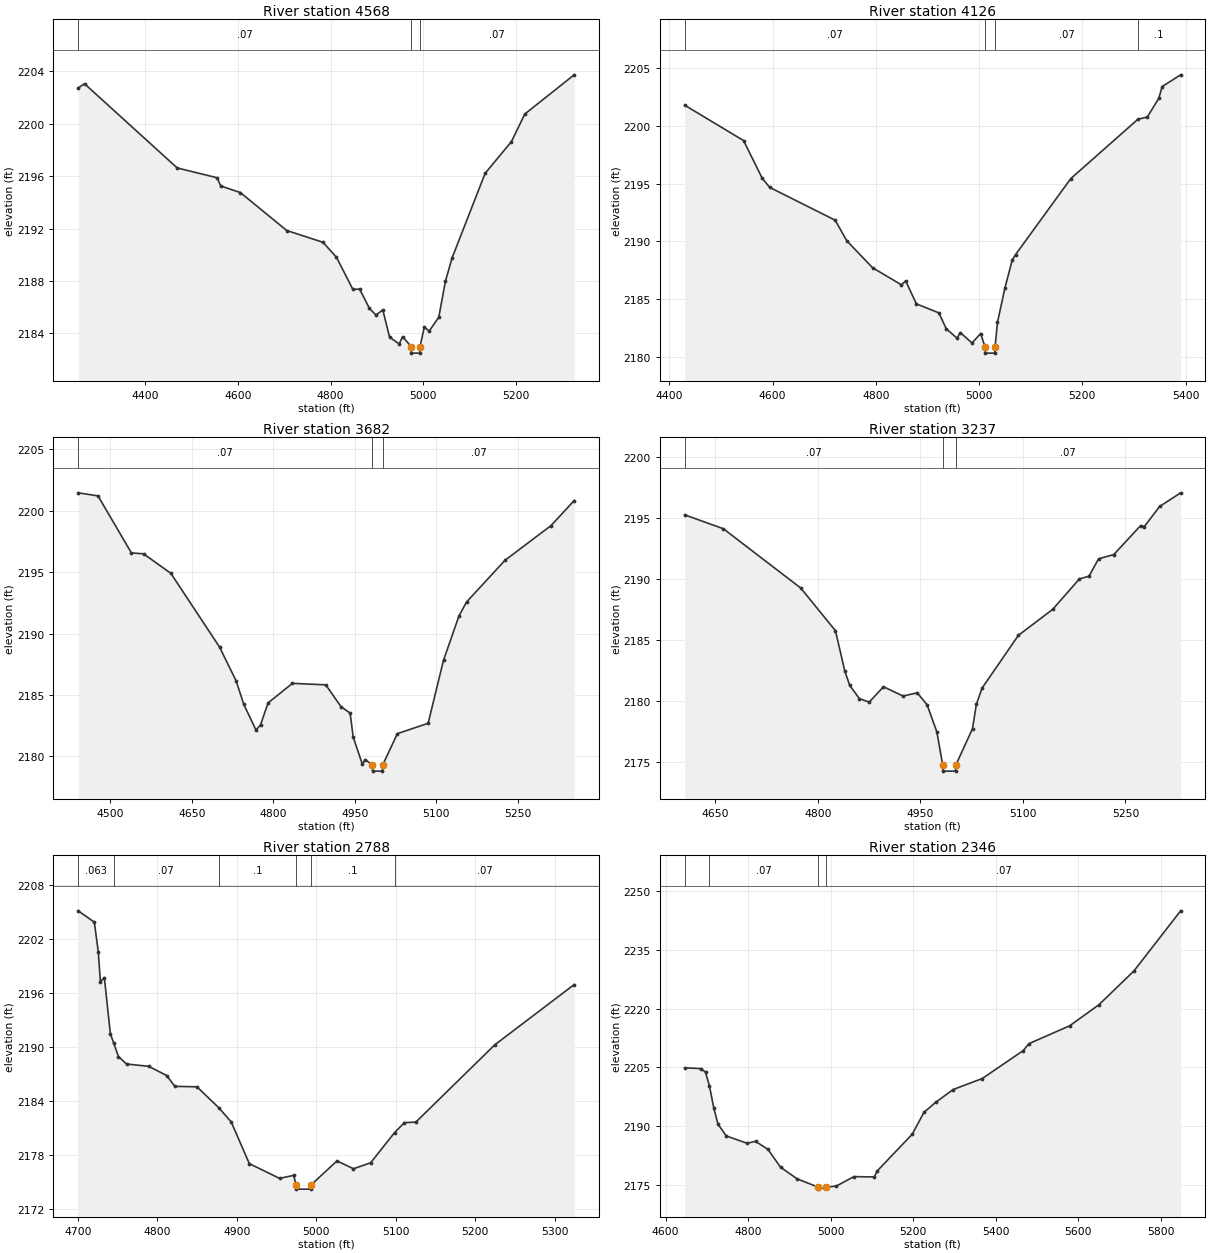
Type RM Length L Ch R = 1,4568,442,442,442
BEGIN DESCRIPTION:
Stream0112 9.0
END DESCRIPTION:
XS GIS Cut Line= 3
      1767574.98     13938175.03      1768025.00     13937575.00
      1768275.00     13937375.00
#Sta/Elev= 30
  4255.2 2202.72  4268.8 2203.04  4468.8 2196.62  4555.2 2195.87  4562.5 2195.25
  4605.2 2194.74  4705.2 2191.85  4783.4 2190.95  4812.5 2189.81  4847.9 2187.36
  4862.5 2187.38  4883.4 2185.92  4897.9 2185.40  4912.5 2185.80  4927.1 2183.72
  4947.9 2183.20  4955.2 2183.75  4973.8 2183.00  4974.3 2182.50  4992.4 2182.50
  4992.9 2183.00  5002.1 2184.50  5012.4 2184.17  5033.3 2185.24  5047.7 2187.99
  5062.1 2189.77  5133.3 2196.21  5190.1 2198.63  5218.9 2200.73  5325.4 2203.72
#Mann=3,-1,0
  4255.2    0.07       0  4973.8    0.05       0  4992.9    0.07       0
Bank Sta=4973.8,4992.9
Exp/Cntr=0.3,0.1

Type RM Length L Ch R = 1,4126,444,444,444
BEGIN DESCRIPTION:
Stream0112 8.0
END DESCRIPTION:
XS GIS Cut Line= 3
      1767825.01     13938274.99      1768275.00     13937925.00
      1768575.01     13937674.99
#Sta/Elev= 30
  4429.7 2201.81  4543.7 2198.74  4579.9 2195.47  4594.4 2194.68  4721.1 2191.84
  4743.7 2190.05  4793.5 2187.72  4849.6 2186.23  4857.7 2186.58  4878.5 2184.58
  4922.0 2183.80  4936.4 2182.42  4957.2 2181.61  4963.6 2182.09  4986.2 2181.19
  5003.0 2182.01  5011.7 2180.81  5012.2 2180.31  5030.3 2180.31  5030.8 2180.81
  5035.6 2182.98  5049.9 2185.94  5064.2 2188.39  5070.7 2188.86  5177.5 2195.44
  5307.4 2200.58  5325.9 2200.79  5348.0 2202.40  5354.5 2203.42  5390.3 2204.44
#Mann=4,-1,0
  4429.7    0.07       0  5011.7    0.05       0  5030.8    0.07       0
  5307.4     0.1       0
Bank Sta=5011.7,5030.8
Exp/Cntr=0.3,0.1

Type RM Length L Ch R = 1,3682,445,445,445
BEGIN DESCRIPTION:
Stream0112 7.0
END DESCRIPTION:
XS GIS Cut Line= 3
      1768074.96     13938475.02      1768575.00     13938225.00
      1768824.99     13937975.01
#Sta/Elev= 30
  4440.9 2201.45  4477.3 2201.20  4538.8 2196.56  4561.1 2196.49  4611.4 2194.90
  4700.9 2188.91  4731.6 2186.14  4745.6 2184.24  4768.0 2182.15  4776.4 2182.58
  4790.3 2184.36  4835.1 2185.95  4896.5 2185.83  4924.5 2184.05  4941.3 2183.53
  4946.9 2181.58  4963.6 2179.39  4969.2 2179.75  4982.0 2179.31  4982.5 2178.81
  5000.7 2178.81  5001.2 2179.31  5028.2 2181.86  5084.8 2182.70  5113.1 2187.83
  5141.4 2191.42  5155.5 2192.57  5226.2 2195.96  5311.1 2198.79  5353.5 2200.82
#Mann=3,-1,0
  4440.9    0.07       0  4982.0    0.05       0  5001.2    0.07       0
Bank Sta=4982,5001.2
Exp/Cntr=0.3,0.1

Type RM Length L Ch R = 1,3237,449,449,449
BEGIN DESCRIPTION:
Stream0112 6.0
END DESCRIPTION:
XS GIS Cut Line= 3
      1768524.98     13938825.01      1768825.00     13938575.00
      1769124.96     13938425.02
#Sta/Elev= 30
  4604.9 2195.27  4661.5 2194.13  4774.8 2189.26  4825.6 2185.75  4839.2 2182.46
  4846.4 2181.27  4860.7 2180.17  4875.0 2179.89  4895.9 2181.15  4924.5 2180.39
  4945.3 2180.65  4959.6 2179.68  4974.0 2177.45  4982.6 2174.72  4983.1 2174.22
  5001.3 2174.22  5001.8 2174.72  5026.2 2177.71  5031.8 2179.70  5040.2 2181.04
  5093.3 2185.37  5143.6 2187.51  5182.7 2190.01  5196.7 2190.23  5210.7 2191.66
  5233.0 2192.01  5272.1 2194.38  5277.7 2194.31  5300.1 2195.96  5330.8 2197.08
#Mann=3,-1,0
  4604.9    0.07       0  4982.6    0.05       0  5001.8    0.07       0
Bank Sta=4982.6,5001.8
Exp/Cntr=0.3,0.1

Type RM Length L Ch R = 1,2788,442,442,442
BEGIN DESCRIPTION:
Stream0112 5.0
END DESCRIPTION:
XS GIS Cut Line= 3
      1768975.00     13939224.98      1769025.00     13938925.00
      1769225.02     13938674.98
#Sta/Elev= 30
  4700.2 2205.17  4720.5 2203.91  4725.5 2200.59  4728.1 2197.28  4733.1 2197.74
  4740.7 2191.48  4744.7 2190.49  4750.9 2188.95  4761.0 2188.12  4788.9 2187.86
  4811.7 2186.83  4821.8 2185.63  4849.7 2185.58  4876.9 2183.27  4892.8 2181.67
  4915.6 2177.03  4953.6 2175.39  4971.4 2175.72  4974.4 2174.69  4974.9 2174.19
  4993.2 2174.19  4993.7 2174.69  5025.9 2177.33  5046.7 2176.46  5068.3 2177.12
  5098.5 2180.49  5110.8 2181.59  5125.2 2181.65  5224.4 2190.24  5324.5 2196.96
#Mann=6,-1,0
  4700.2   0.063       0  4744.7    0.07       0  4876.9     0.1       0
  4974.4    0.05       0  4993.7     0.1       0  5098.5    0.07       0
Bank Sta=4974.4,4993.7
Exp/Cntr=0.3,0.1

Type RM Length L Ch R = 1,2346,435,435,435
BEGIN DESCRIPTION:
Stream0112 4.0
END DESCRIPTION:
XS GIS Cut Line= 3
      1768974.98     13939275.00      1769325.00     13939225.00
      1769925.00     13938625.00
#Sta/Elev= 30
  4646.2 2204.92  4686.6 2204.70  4696.7 2203.77  4706.1 2200.34  4716.9 2194.59
  4727.0 2190.53  4747.2 2187.52  4797.7 2185.67  4817.9 2186.17  4848.2 2184.09
  4878.6 2179.56  4919.0 2176.58  4969.9 2174.47  4970.4 2173.97  4989.2 2174.47
  5013.9 2174.75  5056.3 2177.16  5105.8 2177.08  5112.9 2178.61  5197.8 2187.98
  5226.0 2193.52  5254.3 2196.09  5296.8 2199.36  5367.5 2202.18  5466.5 2209.28
  5480.6 2211.07  5579.6 2215.64  5650.3 2221.00  5735.2 2229.62  5848.3 2244.95
#Mann=4,-1,0
  4646.2   0.063       0  4706.1    0.07       0  4969.9    0.05       0
  4989.2    0.07       0
Bank Sta=4969.9,4989.2
Exp/Cntr=0.3,0.1

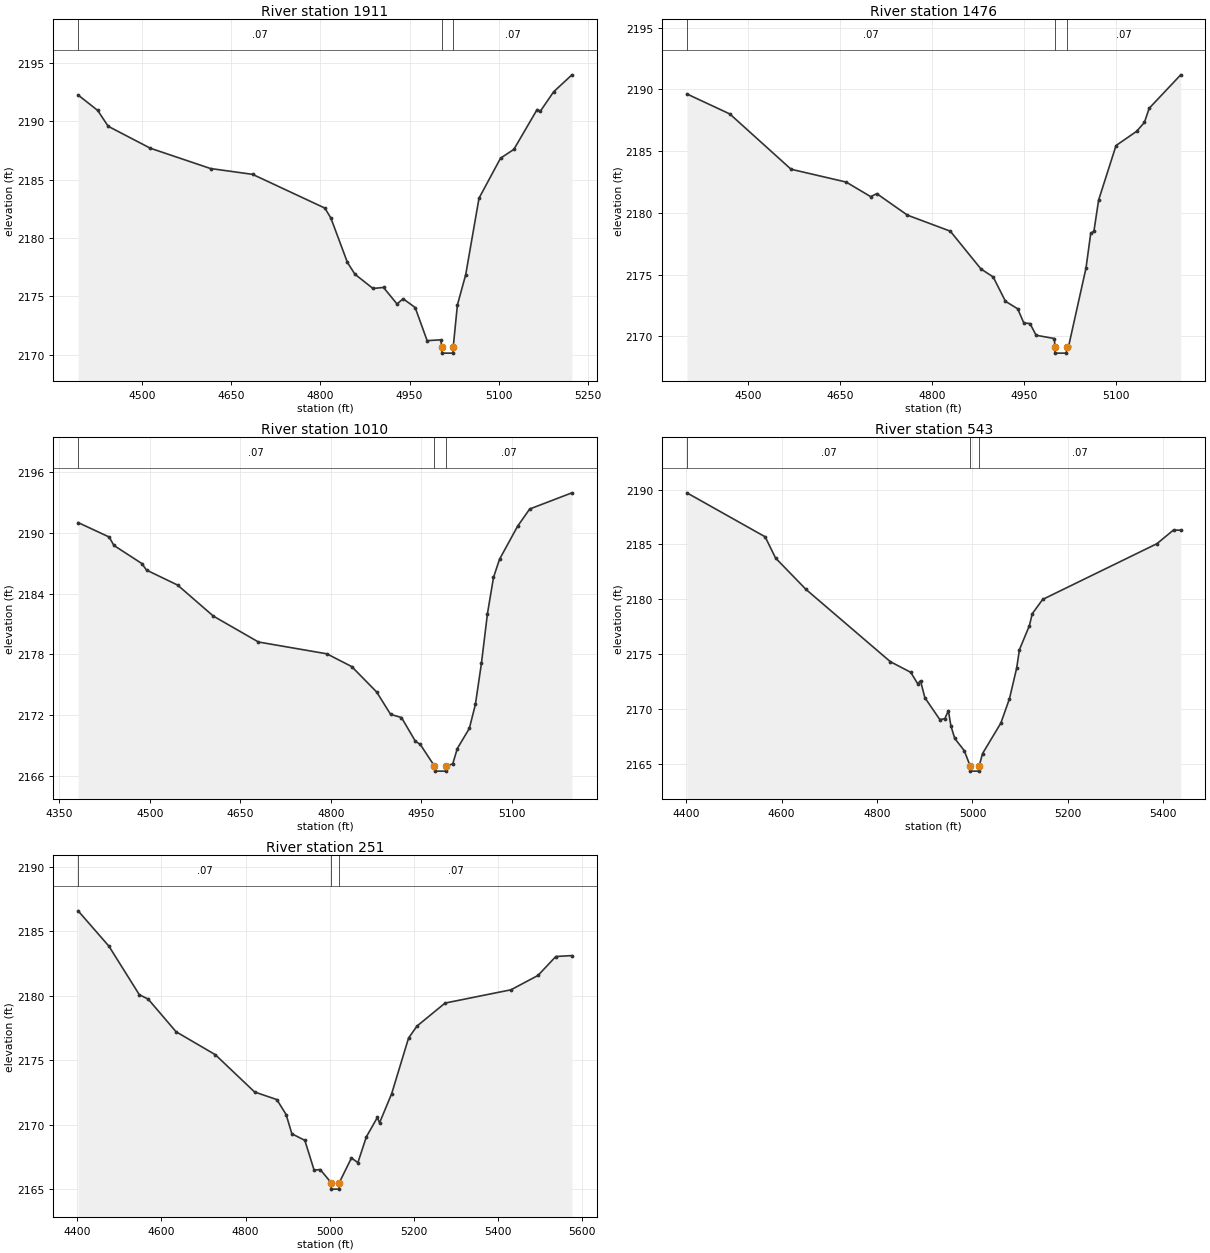
Type RM Length L Ch R = 1,1911,435,435,435
BEGIN DESCRIPTION:
Stream0112 3.0
END DESCRIPTION:
XS GIS Cut Line= 3
      1768974.97     13939625.00      1769575.00     13939525.00
      1769774.99     13939425.00
#Sta/Elev= 30
  4391.7 2192.25  4424.7 2190.93  4442.4 2189.57  4513.4 2187.69  4614.8 2185.95
  4685.7 2185.45  4807.4 2182.56  4817.5 2181.71  4845.4 2177.90  4858.1 2176.89
  4888.5 2175.67  4906.2 2175.76  4929.0 2174.34  4939.2 2174.79  4959.5 2174.04
  4979.7 2171.20  5002.8 2171.27  5004.3 2170.63  5004.8 2170.13  5023.1 2170.13
  5023.6 2170.63  5030.7 2174.26  5044.7 2176.86  5067.1 2183.41  5103.4 2186.84
  5125.8 2187.59  5164.9 2191.00  5170.5 2190.87  5192.9 2192.53  5223.6 2193.98
#Mann=3,-1,0
  4391.7    0.07       0  5004.3    0.05       0  5023.6    0.07       0
Bank Sta=5004.3,5023.6
Exp/Cntr=0.3,0.1

Type RM Length L Ch R = 1,1476,466,466,466
BEGIN DESCRIPTION:
Stream0112 2.0
END DESCRIPTION:
XS GIS Cut Line= 3
      1769075.04     13939925.00      1769675.00     13939925.00
      1769874.98     13939975.00
#Sta/Elev= 30
  4400.0 2189.63  4470.0 2188.01  4570.0 2183.53  4660.0 2182.49  4700.0 2181.31
  4710.0 2181.55  4760.0 2179.81  4830.0 2178.51  4880.0 2175.45  4900.0 2174.80
  4920.0 2172.83  4940.0 2172.22  4950.0 2171.07  4960.0 2171.03  4970.0 2170.08
  5000.0 2169.81  5000.6 2169.13  5001.1 2168.63  5019.5 2168.63  5020.0 2169.13
  5023.2 2169.21  5051.5 2175.53  5059.2 2178.34  5064.4 2178.51  5072.1 2181.04
  5100.5 2185.45  5134.0 2186.60  5146.8 2187.32  5154.6 2188.47  5206.1 2191.18
#Mann=3,-1,0
  4400.0    0.07       0  5000.6    0.05       0  5020.0    0.07       0
Bank Sta=5000.6,5020
Exp/Cntr=0.3,0.1

Type RM Length L Ch R = 1,1010,467,467,467
BEGIN DESCRIPTION:
Stream0112 1.0
END DESCRIPTION:
XS GIS Cut Line= 3
      1769025.01     13940225.00      1769625.00     13940375.00
      1769825.05     13940375.00
#Sta/Elev= 30
  4381.2 2191.04  4432.7 2189.61  4440.5 2188.78  4486.8 2186.99  4494.6 2186.34
  4546.1 2184.86  4605.4 2181.79  4680.1 2179.23  4793.5 2178.06  4834.7 2176.80
  4876.0 2174.29  4899.2 2172.07  4917.2 2171.76  4940.4 2169.40  4948.1 2169.12
  4971.9 2166.96  4972.4 2166.46  4990.8 2166.46  4991.3 2166.96  5002.2 2167.18
  5009.7 2168.69  5029.7 2170.69  5039.7 2173.05  5049.7 2177.11  5059.7 2182.03
  5069.7 2185.61  5079.7 2187.41  5109.7 2190.68  5129.7 2192.38  5199.7 2193.98
#Mann=3,-1,0
  4381.2    0.07       0  4971.9    0.05       0  4991.3    0.07       0
Bank Sta=4971.9,4991.3
Exp/Cntr=0.3,0.1

Type RM Length L Ch R = 1,543,292,292,292
BEGIN DESCRIPTION:
Stream0112 0.1
END DESCRIPTION:
XS GIS Cut Line= 4
      1768943.45     13940425.04      1769316.25     13940742.60
      1769541.31     13940809.70      1769818.51     13940669.51
#Sta/Elev= 30
  4401.4 2189.70  4565.4 2185.69  4587.3 2183.75  4651.1 2180.89  4827.9 2174.30
  4870.7 2173.33  4885.0 2172.30  4891.1 2172.56  4900.2 2171.02  4931.6 2169.02
  4942.0 2169.10  4949.6 2169.83  4954.8 2168.45  4962.9 2167.30  4982.8 2166.19
  4994.9 2164.82  4995.4 2164.32  5013.8 2164.32  5014.3 2164.82  5021.1 2165.92
  5059.5 2168.70  5077.6 2170.93  5092.7 2173.72  5098.5 2175.40  5119.4 2177.59
  5125.3 2178.67  5147.2 2179.98  5386.7 2185.06  5421.5 2186.31  5436.6 2186.29
#Mann=3,-1,0
  4401.4    0.07       0  4994.9    0.05       0  5014.3    0.07       0
Bank Sta=4994.9,5014.3
Exp/Cntr=0.3,0.1

Type RM Length L Ch R = 1,251,0,0,0
BEGIN DESCRIPTION:
Stream0112 0.0
END DESCRIPTION:
XS GIS Cut Line= 5
      1768898.55     13940580.58      1769135.91     13940939.05
      1769339.95     13941044.18      1769503.01     13941031.19
      1769774.67     13940810.72
#Sta/Elev= 30
  4402.3 2186.59  4475.5 2183.85  4547.7 2180.09  4568.7 2179.75  4634.9 2177.22
  4728.2 2175.44  4821.5 2172.55  4874.3 2171.96  4896.4 2170.80  4910.0 2169.31
  4940.8 2168.80  4962.9 2166.49  4977.4 2166.54  5003.2 2165.52  5003.7 2165.02
  5022.1 2165.02  5022.6 2165.52  5051.6 2167.44  5066.8 2167.07  5086.9 2169.07
  5113.2 2170.58  5118.2 2170.15  5147.1 2172.42  5187.2 2176.73  5207.3 2177.66
  5273.9 2179.44  5430.5 2180.47  5494.5 2181.58  5537.0 2183.05  5575.2 2183.12
#Mann=3,-1,0
  4402.3    0.07       0  5003.2    0.05       0  5022.6    0.07       0
Bank Sta=5003.2,5022.6
Exp/Cntr=0.3,0.1

Chan Stop Cuts=-1