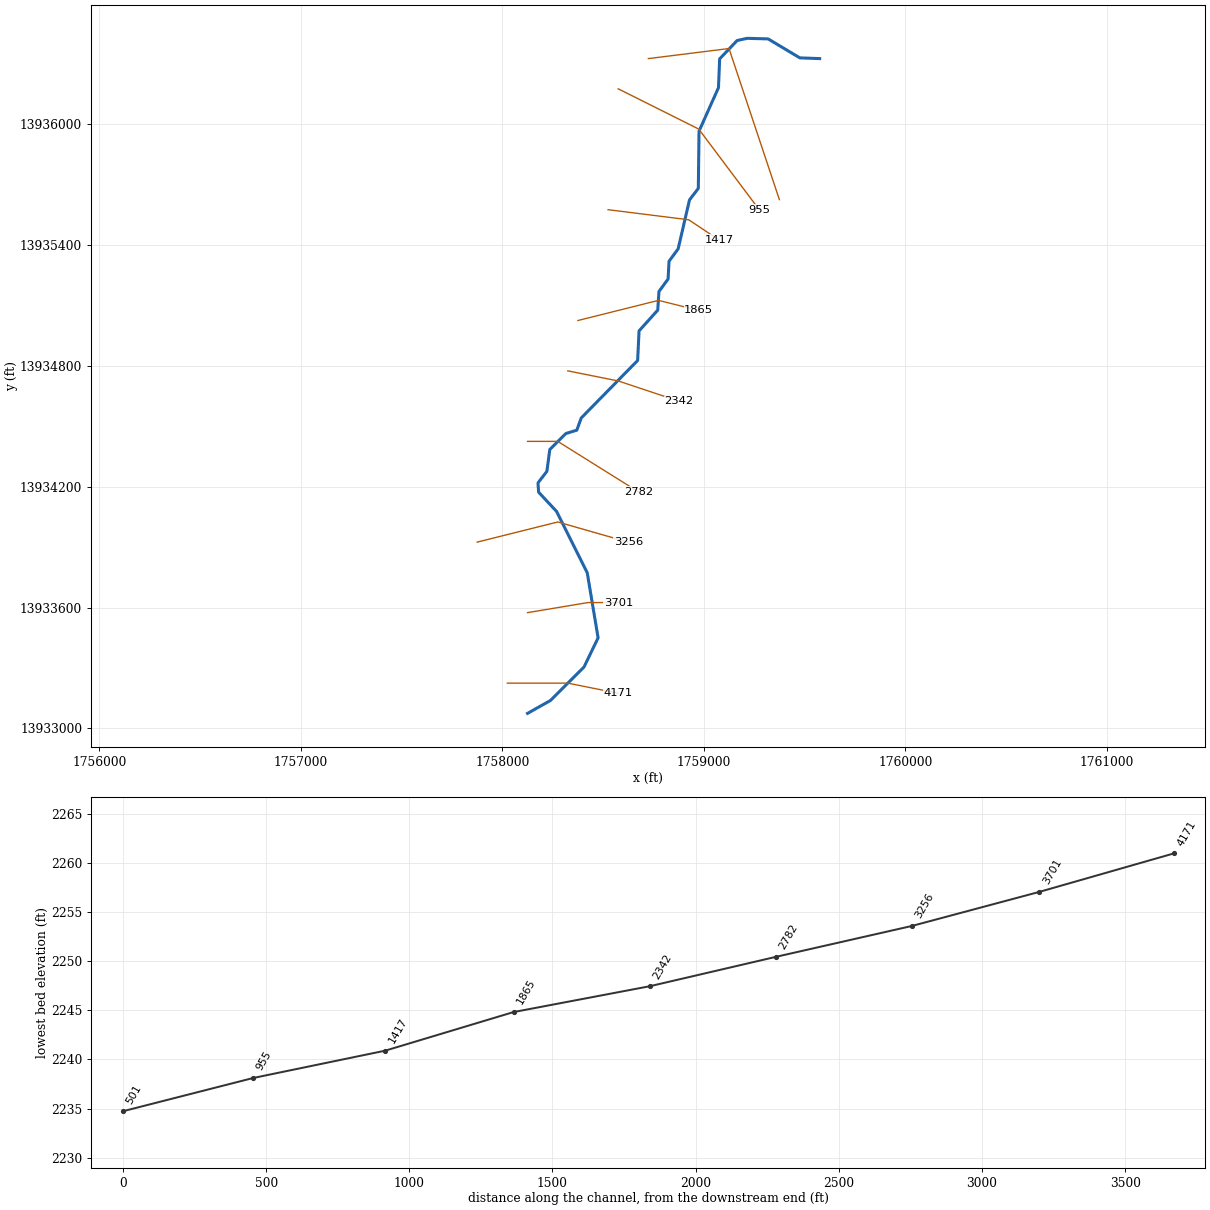
--- Stream0113.prj (project) ---

Proj Title=Stream0113 Base Level Engineering
Current Plan=p01
Default Exp/Contr=0.3,0.1
English Units
Geom File=g01
Flow File=f01
Plan File=p01
BEGIN DESCRIPTION:
Stream0113
END DESCRIPTION:

--- Stream0113.p01 (plan) ---

Plan Title=Multiple Run
Short Identifier=Multiple
Geom File=g01
Flow File=f01
Subcritical Flow
K Sum by GR= 0
Std Step Tol= 0.01
Critical Tol= 0.01
Num of Std Step Trials= 20
Max Error Tol= 0.3
Flow Tol Ratio= 0.001
Split Flow NTrial= 30
Split Flow Tol= 0.02
Split Flow Ratio= 0.02
Log Output Level= 0
Friction Slope Method= 1
Unsteady Friction Slope Method= 2
Unsteady Bridges Friction Slope Method= 1
Parabolic Critical Depth
Global Vel Dist=  1 , 1 , 1
Global Log Level= 0
CheckData=True
Encroach Param= -1, 0, 0, 0
BEGIN DESCRIPTION:
Multiple Run
END DESCRIPTION:

--- Stream0113.f01 (steady flow) ---

Flow Title=Multiple
Number of Profiles=7
Profile Names=10-year,25-year,50-year,1pct_min,100-year,1pct_plu,500-year
River Rch & RM= Stream0113,Reach-1,4171
    1175    2019    2823    1904    3800    7581    6814
Boundary for River Rch & Prof#=Stream0113,Reach-1,1
Up Type=0
Dn Type=3
Dn Slope=0.005
Boundary for River Rch & Prof#=Stream0113,Reach-1,2
Up Type=0
Dn Type=3
Dn Slope=0.005
Boundary for River Rch & Prof#=Stream0113,Reach-1,3
Up Type=0
Dn Type=3
Dn Slope=0.005
Boundary for River Rch & Prof#=Stream0113,Reach-1,4
Up Type=0
Dn Type=3
Dn Slope=0.005
Boundary for River Rch & Prof#=Stream0113,Reach-1,5
Up Type=0
Dn Type=3
Dn Slope=0.005
Boundary for River Rch & Prof#=Stream0113,Reach-1,6
Up Type=0
Dn Type=3
Dn Slope=0.005
Boundary for River Rch & Prof#=Stream0113,Reach-1,7
Up Type=0
Dn Type=3
Dn Slope=0.005

--- Stream0113.g01 (geometry) ---

Geom Title=Existing Conditions

River Reach=Stream0113,Reach-1
Reach XY= 30
      1758125.00     13933075.00      1758238.23     13933138.57
      1758405.22     13933304.91      1758475.24     13933449.92
      1758421.24     13933773.44      1758269.15     13934077.29
      1758180.10     13934172.71      1758176.78     13934218.87
      1758221.11     13934276.59      1758235.51     13934384.81
      1758315.56     13934464.12      1758369.38     13934480.62
      1758391.73     13934541.48      1758671.46     13934826.47
      1758678.56     13934973.53      1758771.38     13935076.50
      1758777.36     13935169.02      1758822.65     13935230.97
      1758827.35     13935319.03      1758872.65     13935380.97
      1758928.86     13935623.40      1758972.74     13935680.94
      1758976.22     13935964.50      1759072.73     13936180.94
      1759078.54     13936323.54      1759165.18     13936414.54
      1759214.81     13936425.55      1759319.07     13936422.77
      1759476.50     13936328.63      1759575.00     13936325.00

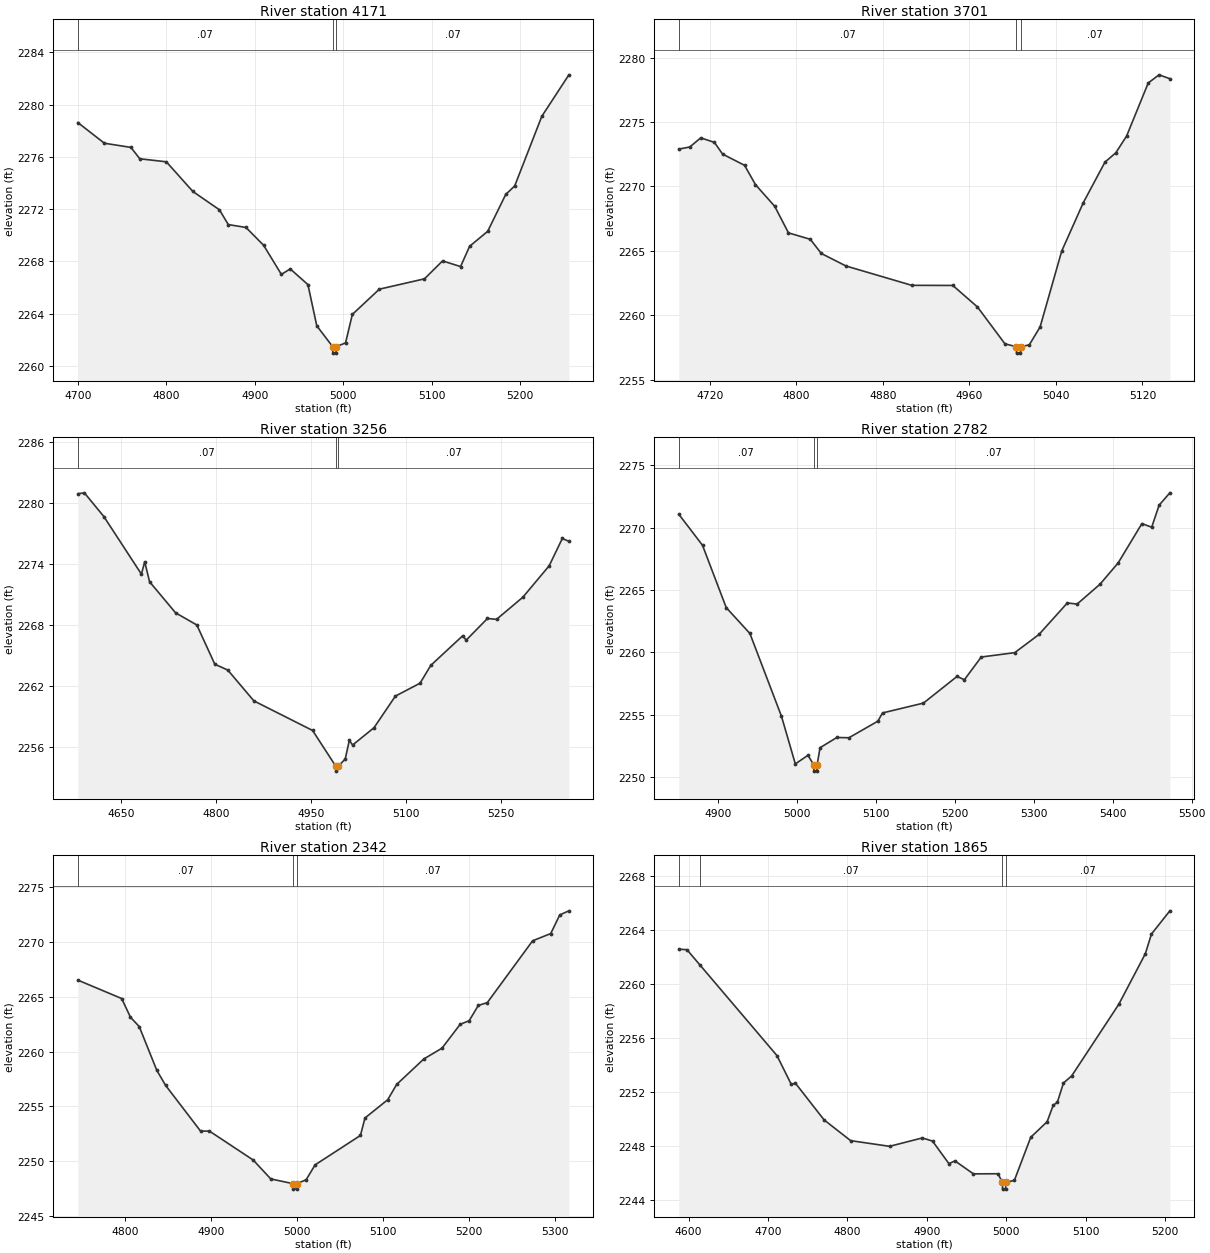
Type RM Length L Ch R = 1,4171,470,470,470
BEGIN DESCRIPTION:
Stream0113 9.0
END DESCRIPTION:
XS GIS Cut Line= 3
      1758025.05     13933225.00      1758325.00     13933225.00
      1758575.00     13933175.00
#Sta/Elev= 30
  4700.0 2278.62  4730.0 2277.04  4760.0 2276.72  4770.0 2275.85  4800.0 2275.62
  4830.0 2273.35  4860.0 2271.95  4870.0 2270.82  4890.0 2270.60  4910.0 2269.23
  4930.0 2267.01  4940.0 2267.43  4960.0 2266.23  4970.0 2263.08  4987.9 2261.49
  4988.2 2260.99  4991.8 2260.99  4992.0 2261.49  5002.5 2261.77  5010.2 2263.95
  5040.7 2265.88  5091.7 2266.67  5112.1 2268.04  5132.5 2267.61  5142.7 2269.16
  5163.1 2270.30  5183.5 2273.12  5193.7 2273.78  5224.3 2279.10  5254.9 2282.27
#Mann=3,-1,0
  4700.0    0.07       0  4987.9    0.05       0  4992.0    0.07       0
Bank Sta=4987.9,4992
Exp/Cntr=0.3,0.1

Type RM Length L Ch R = 1,3701,445,445,445
BEGIN DESCRIPTION:
Stream0113 8.0
END DESCRIPTION:
XS GIS Cut Line= 3
      1758125.02     13933575.00      1758425.00     13933625.00
      1758574.98     13933625.00
#Sta/Elev= 30
  4691.3 2272.90  4701.4 2273.06  4711.6 2273.77  4724.2 2273.42  4731.8 2272.51
  4752.1 2271.64  4762.2 2270.14  4780.0 2268.46  4792.7 2266.40  4812.9 2265.90
  4823.1 2264.80  4845.9 2263.83  4906.7 2262.33  4944.7 2262.32  4967.5 2260.65
  4992.9 2257.79  5003.4 2257.57  5003.6 2257.07  5007.2 2257.07  5007.5 2257.57
  5015.4 2257.71  5025.4 2259.10  5045.4 2264.99  5065.4 2268.75  5085.4 2271.89
  5095.4 2272.61  5105.4 2273.91  5125.4 2278.03  5135.4 2278.66  5145.4 2278.36
#Mann=3,-1,0
  4691.3    0.07       0  5003.4    0.05       0  5007.5    0.07       0
Bank Sta=5003.4,5007.5
Exp/Cntr=0.3,0.1

Type RM Length L Ch R = 1,3256,474,474,474
BEGIN DESCRIPTION:
Stream0113 7.0
END DESCRIPTION:
XS GIS Cut Line= 3
      1757875.00     13933925.00      1758275.00     13934025.00
      1758624.98     13933925.01
#Sta/Elev= 30
  4581.6 2280.89  4591.9 2280.98  4622.8 2278.64  4682.1 2272.98  4687.3 2274.20
  4695.0 2272.23  4736.2 2269.17  4769.7 2267.98  4798.1 2264.12  4818.7 2263.54
  4859.9 2260.51  4952.7 2257.60  4989.2 2254.10  4989.5 2253.60  4993.4 2254.10
  5004.3 2254.79  5010.8 2256.63  5016.0 2256.17  5049.8 2257.87  5083.6 2260.98
  5122.6 2262.25  5139.5 2264.00  5190.2 2266.93  5195.4 2266.48  5229.2 2268.62
  5243.5 2268.53  5285.1 2270.71  5326.7 2273.80  5347.5 2276.49  5357.9 2276.21
#Mann=3,-1,0
  4581.6    0.07       0  4989.2    0.05       0  4993.4    0.07       0
Bank Sta=4989.2,4993.4
Exp/Cntr=0.3,0.1

Type RM Length L Ch R = 1,2782,440,440,440
BEGIN DESCRIPTION:
Stream0113 6.0
END DESCRIPTION:
XS GIS Cut Line= 3
      1758125.04     13934425.00      1758275.00     13934425.00
      1758675.04     13934174.98
#Sta/Elev= 30
  4850.7 2271.08  4880.7 2268.59  4910.7 2263.59  4940.7 2261.51  4980.7 2254.86
  4998.2 2251.04  5014.2 2251.73  5021.6 2250.96  5021.8 2250.46  5025.5 2250.46
  5025.8 2250.96  5029.5 2252.34  5050.8 2253.16  5066.1 2253.14  5102.7 2254.47
  5108.6 2255.13  5160.4 2255.92  5202.9 2258.06  5212.3 2257.80  5233.6 2259.62
  5276.0 2259.97  5306.7 2261.43  5342.6 2263.96  5355.0 2263.87  5383.9 2265.46
  5406.9 2267.17  5437.0 2270.33  5449.4 2270.04  5458.8 2271.81  5472.4 2272.80
#Mann=3,-1,0
  4850.7    0.07       0  5021.6    0.05       0  5025.8    0.07       0
Bank Sta=5021.6,5025.8
Exp/Cntr=0.3,0.1

Type RM Length L Ch R = 1,2342,477,477,477
BEGIN DESCRIPTION:
Stream0113 5.0
END DESCRIPTION:
XS GIS Cut Line= 3
      1758325.00     13934775.00      1758575.00     13934725.00
      1758875.02     13934624.99
#Sta/Elev= 30
  4745.0 2266.51  4796.0 2264.83  4806.2 2263.13  4816.4 2262.28  4836.8 2258.30
  4847.0 2256.93  4887.8 2252.75  4898.0 2252.76  4949.0 2250.12  4969.4 2248.40
  4995.2 2247.97  4995.5 2247.47  4999.4 2247.47  4999.7 2247.97  5010.5 2248.32
  5021.0 2249.68  5073.7 2252.36  5079.0 2253.95  5105.4 2255.61  5115.9 2257.01
  5147.5 2259.33  5168.6 2260.31  5189.7 2262.48  5200.2 2262.81  5210.8 2264.20
  5221.3 2264.46  5274.0 2270.09  5295.1 2270.75  5305.6 2272.45  5316.2 2272.82
#Mann=3,-1,0
  4745.0    0.07       0  4995.2    0.05       0  4999.7    0.07       0
Bank Sta=4995.2,4999.7
Exp/Cntr=0.3,0.1

Type RM Length L Ch R = 1,1865,448,448,448
BEGIN DESCRIPTION:
Stream0113 4.0
END DESCRIPTION:
XS GIS Cut Line= 3
      1758375.05     13935025.01      1758775.00     13935125.00
      1758974.98     13935075.00
#Sta/Elev= 30
  4587.7 2262.60  4598.0 2262.56  4614.6 2261.41  4711.3 2254.72  4729.4 2252.58
  4734.5 2252.68  4770.6 2249.96  4804.1 2248.42  4853.1 2248.00  4894.3 2248.62
  4907.2 2248.39  4927.8 2246.72  4935.5 2246.92  4958.7 2245.96  4989.7 2245.97
  4995.1 2245.33  4995.4 2244.83  4999.3 2244.83  4999.6 2245.33  5010.3 2245.48
  5030.9 2248.67  5051.5 2249.82  5059.2 2251.04  5064.4 2251.26  5072.1 2252.69
  5082.4 2253.21  5141.7 2258.51  5175.2 2262.26  5182.9 2263.72  5206.1 2265.44
#Mann=4,-1,0
  4587.7     0.1       0  4614.6    0.07       0  4995.1    0.05       0
  4999.6    0.07       0
Bank Sta=4995.1,4999.6
Exp/Cntr=0.3,0.1

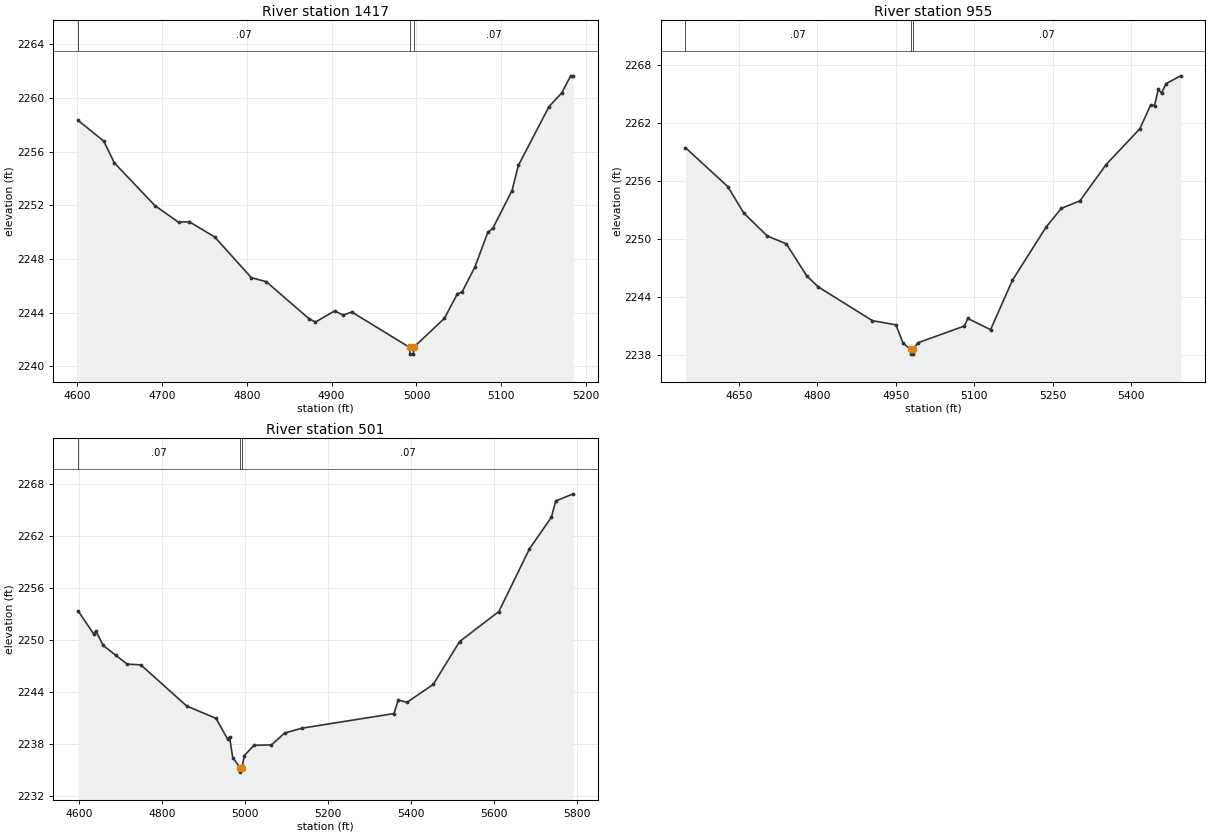
Type RM Length L Ch R = 1,1417,462,462,462
BEGIN DESCRIPTION:
Stream0113 3.0
END DESCRIPTION:
XS GIS Cut Line= 3
      1758525.00     13935575.00      1758925.00     13935525.00
      1759075.01     13935424.99
#Sta/Elev= 30
  4601.3 2258.32  4631.5 2256.78  4644.1 2255.15  4692.0 2251.96  4719.7 2250.73
  4732.3 2250.77  4762.5 2249.62  4805.4 2246.60  4823.0 2246.30  4873.4 2243.54
  4881.0 2243.29  4903.6 2244.12  4913.7 2243.81  4923.8 2244.04  4992.0 2241.40
  4992.4 2240.90  4996.3 2240.90  4996.6 2241.40  5033.0 2243.57  5048.0 2245.37
  5054.0 2245.56  5069.0 2247.41  5084.0 2249.97  5090.0 2250.28  5112.6 2253.09
  5120.1 2254.96  5156.1 2259.34  5171.2 2260.37  5181.7 2261.64  5184.7 2261.64
#Mann=3,-1,0
  4601.3    0.07       0  4992.0    0.05       0  4996.6    0.07       0
Bank Sta=4992,4996.6
Exp/Cntr=0.3,0.1

Type RM Length L Ch R = 1,955,454,454,454
BEGIN DESCRIPTION:
Stream0113 2.0
END DESCRIPTION:
XS GIS Cut Line= 3
      1758575.03     13936174.98      1758975.00     13935975.00
      1759275.01     13935574.98
#Sta/Elev= 30
  4547.9 2259.46  4628.9 2255.43  4659.7 2252.68  4704.4 2250.33  4740.7 2249.52
  4779.9 2246.20  4802.2 2245.05  4905.6 2241.57  4950.4 2241.14  4964.3 2239.22
  4978.8 2238.61  4979.1 2238.11  4983.1 2238.11  4983.5 2238.61  4992.3 2239.28
  5081.5 2241.02  5087.8 2241.80  5131.5 2240.64  5173.2 2245.74  5237.8 2251.26
  5267.0 2253.19  5302.4 2253.96  5352.4 2257.71  5417.0 2261.41  5437.8 2263.89
  5445.1 2263.82  5452.4 2265.50  5458.6 2265.10  5467.0 2266.08  5495.1 2266.89
#Mann=3,-1,0
  4547.9    0.07       0  4978.8    0.05       0  4983.5    0.07       0
Bank Sta=4978.8,4983.5
Exp/Cntr=0.3,0.1

Type RM Length L Ch R = 1,501,0,0,0
BEGIN DESCRIPTION:
Stream0113 1.0
END DESCRIPTION:
XS GIS Cut Line= 3
      1758725.01     13936325.00      1759125.00     13936375.00
      1759375.01     13935624.97
#Sta/Elev= 30
  4597.7 2253.37  4635.5 2250.69  4640.5 2251.05  4658.2 2249.38  4688.4 2248.24
  4716.1 2247.21  4748.9 2247.13  4859.7 2242.37  4930.3 2240.94  4958.0 2238.57
  4963.0 2238.78  4970.6 2236.42  4988.4 2235.23  4988.7 2234.73  4993.1 2235.23
  4998.3 2236.64  5021.9 2237.83  5064.0 2237.88  5095.7 2239.25  5137.8 2239.81
  5359.2 2241.50  5369.7 2243.06  5390.8 2242.80  5454.1 2244.87  5517.3 2249.81
  5612.2 2253.29  5686.0 2260.54  5738.7 2264.18  5749.2 2266.06  5791.4 2266.89
#Mann=3,-1,0
  4597.7    0.07       0  4988.4    0.05       0  4993.1    0.07       0
Bank Sta=4988.4,4993.1
Exp/Cntr=0.3,0.1

Chan Stop Cuts=-1