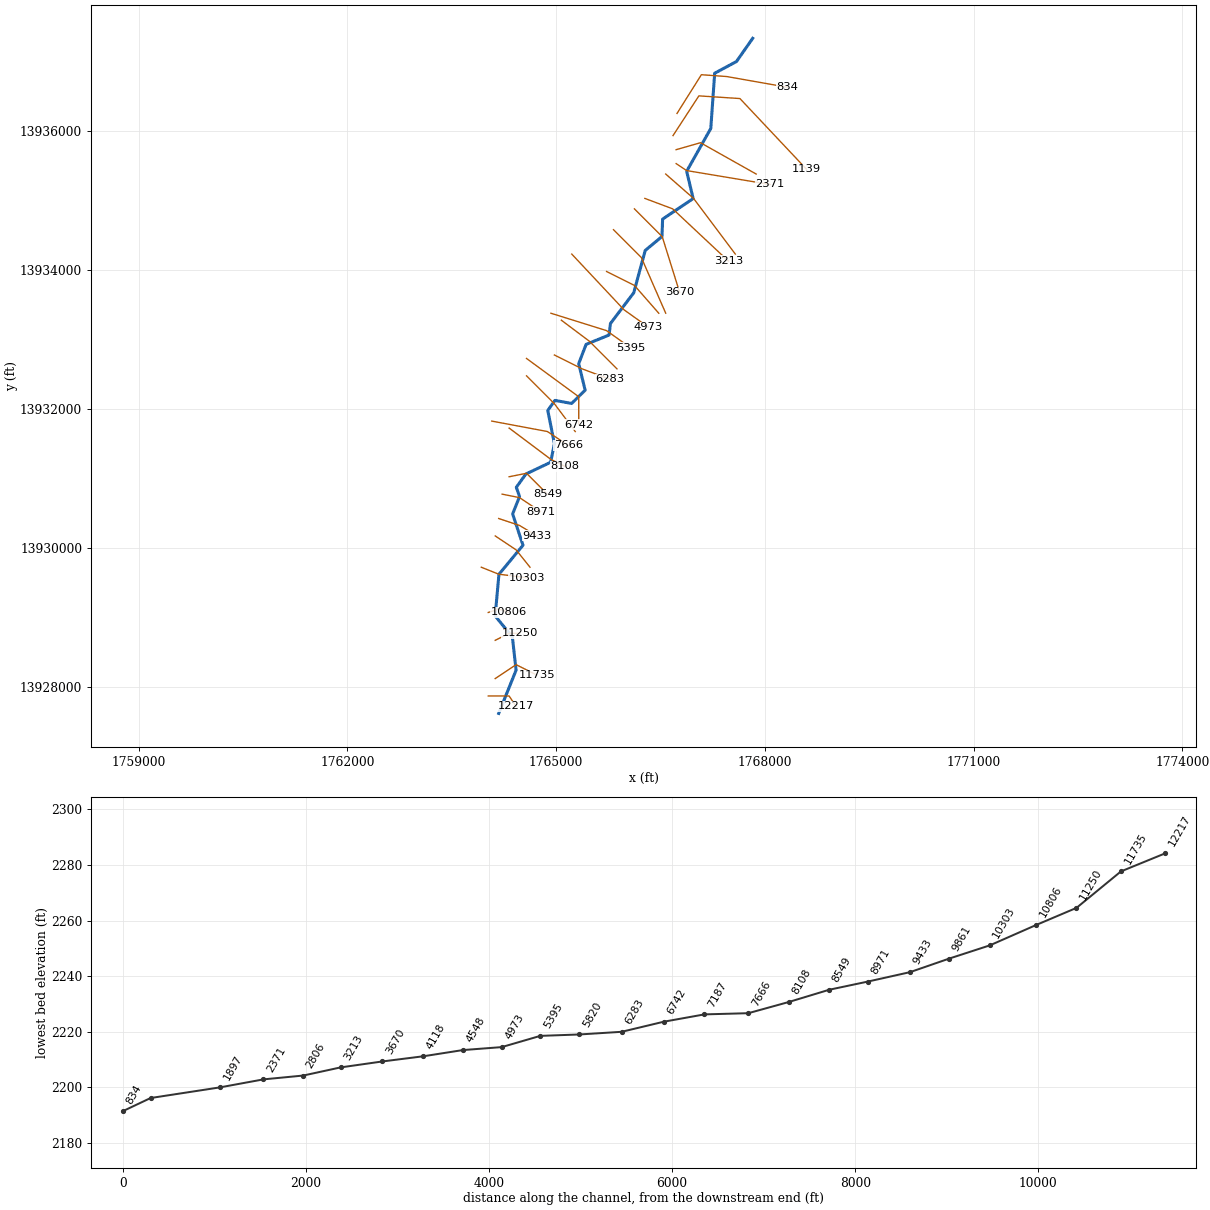
--- Stream0114.prj (project) ---

Proj Title=Stream0114 Base Level Engineering
Current Plan=p01
Default Exp/Contr=0.3,0.1
English Units
Geom File=g01
Flow File=f01
Plan File=p01
BEGIN DESCRIPTION:
Stream0114
END DESCRIPTION:

--- Stream0114.p01 (plan) ---

Plan Title=Multiple Run
Short Identifier=Multiple
Geom File=g01
Flow File=f01
Subcritical Flow
K Sum by GR= 0
Std Step Tol= 0.01
Critical Tol= 0.01
Num of Std Step Trials= 20
Max Error Tol= 0.3
Flow Tol Ratio= 0.001
Split Flow NTrial= 30
Split Flow Tol= 0.02
Split Flow Ratio= 0.02
Log Output Level= 0
Friction Slope Method= 1
Unsteady Friction Slope Method= 2
Unsteady Bridges Friction Slope Method= 1
Parabolic Critical Depth
Global Vel Dist=  1 , 1 , 1
Global Log Level= 0
CheckData=True
Encroach Param= -1, 0, 0, 0
BEGIN DESCRIPTION:
Multiple Run
END DESCRIPTION:

--- Stream0114.f01 (steady flow) ---

Flow Title=Multiple
Number of Profiles=7
Profile Names=10-year,25-year,50-year,1pct_min,100-year,1pct_plu,500-year
River Rch & RM= Stream0114,Reach-1,12217
     275     429     563     358     715    1427    1138
River Rch & RM= Stream0114,Reach-1,10806
    1251    2154    3019    2042    4074    8129    7340
River Rch & RM= Stream0114,Reach-1,7187
    1539    2662    3740    2532    5052   10080    9125
River Rch & RM= Stream0114,Reach-1,1139
    1950    3415    4838    3300    6585   13139   12079
Boundary for River Rch & Prof#=Stream0114,Reach-1,1
Up Type=0
Dn Type=3
Dn Slope=0.005
Boundary for River Rch & Prof#=Stream0114,Reach-1,2
Up Type=0
Dn Type=3
Dn Slope=0.005
Boundary for River Rch & Prof#=Stream0114,Reach-1,3
Up Type=0
Dn Type=3
Dn Slope=0.005
Boundary for River Rch & Prof#=Stream0114,Reach-1,4
Up Type=0
Dn Type=3
Dn Slope=0.005
Boundary for River Rch & Prof#=Stream0114,Reach-1,5
Up Type=0
Dn Type=3
Dn Slope=0.005
Boundary for River Rch & Prof#=Stream0114,Reach-1,6
Up Type=0
Dn Type=3
Dn Slope=0.005
Boundary for River Rch & Prof#=Stream0114,Reach-1,7
Up Type=0
Dn Type=3
Dn Slope=0.005

--- Stream0114.g01 (geometry) ---

Geom Title=Existing Conditions

River Reach=Stream0114,Reach-1
Reach XY= 30
      1764175.00     13927625.00      1764424.93     13928245.03
      1764371.39     13928723.50      1764124.15     13929024.99
      1764178.55     13929623.53      1764524.35     13930040.84
      1764375.08     13930490.39      1764474.90     13930740.40
      1764428.34     13930873.28      1764565.29     13931064.25
      1764921.92     13931233.30      1764975.41     13931500.00
      1764880.11     13931977.29      1764983.48     13932122.37
      1765223.53     13932078.53      1765417.19     13932268.81
      1765324.60     13932650.00      1765430.82     13932927.32
      1765761.37     13933061.63      1765780.80     13933227.30
      1766115.41     13933668.45      1766280.73     13934277.55
      1766521.46     13934476.46      1766530.46     13934727.45
      1766969.61     13935022.32      1766876.21     13935414.49
      1767222.88     13936030.88      1767278.53     13936823.55
      1767591.68     13936991.64      1767825.00     13937325.00

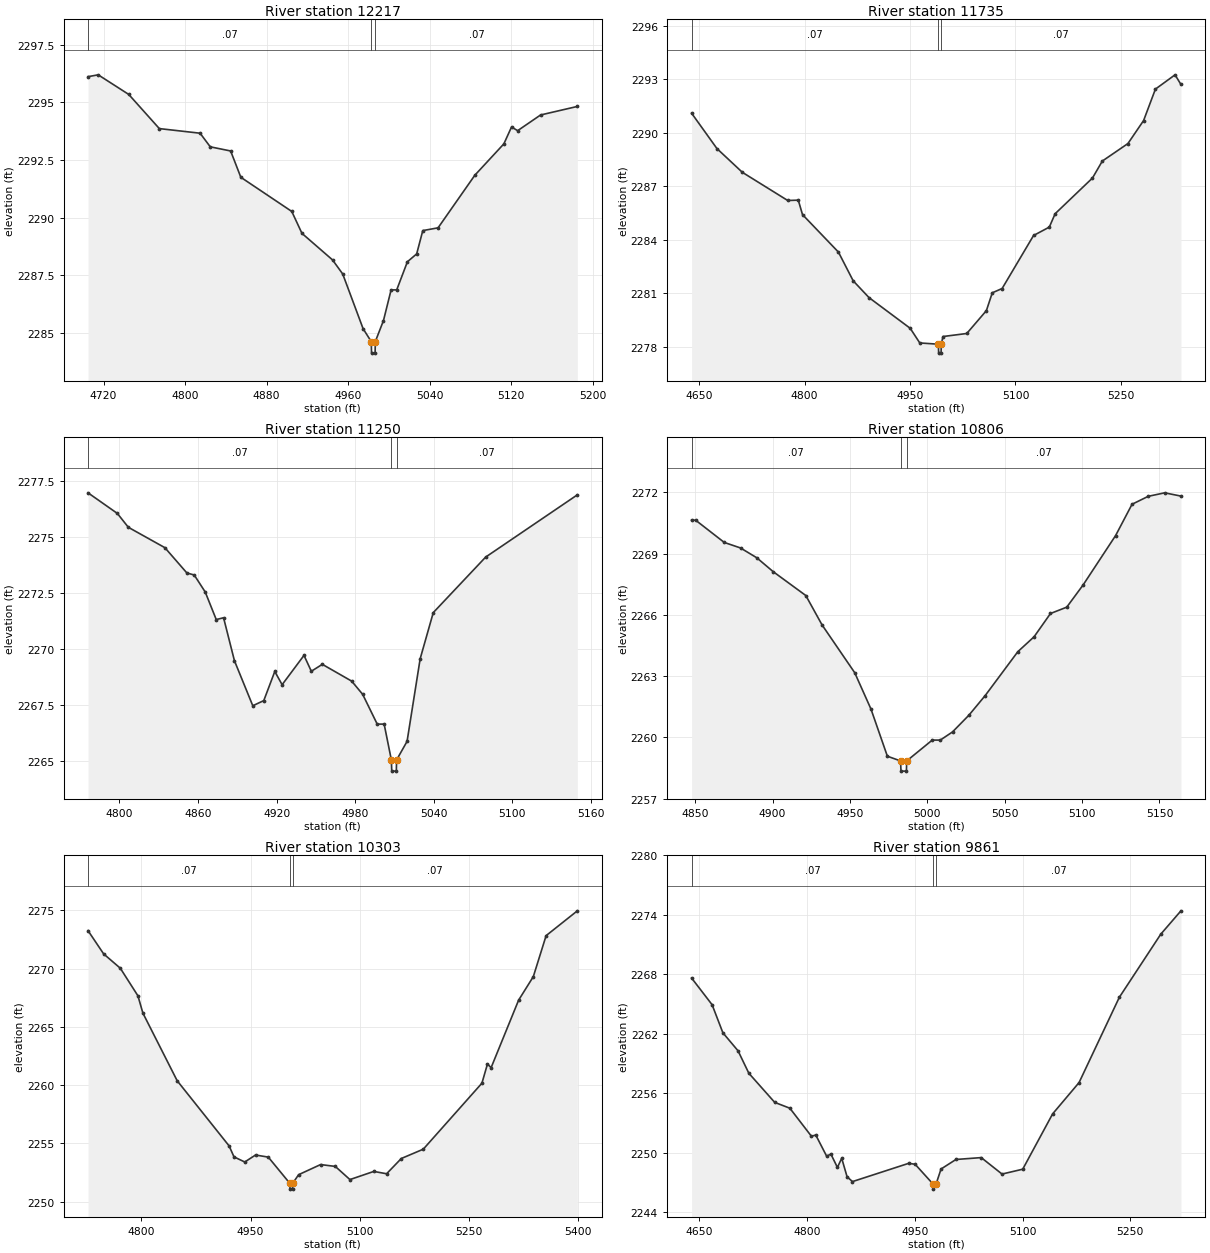
Type RM Length L Ch R = 1,12217,482,482,482
BEGIN DESCRIPTION:
Stream0114 24.0
END DESCRIPTION:
XS GIS Cut Line= 3
      1764024.97     13927875.00      1764325.00     13927875.00
      1764425.00     13927725.00
#Sta/Elev= 30
  4704.7 2296.11  4714.7 2296.19  4744.7 2295.34  4774.7 2293.86  4814.7 2293.66
  4824.7 2293.07  4844.7 2292.89  4854.7 2291.75  4904.7 2290.27  4914.7 2289.32
  4944.7 2288.17  4954.7 2287.56  4974.7 2285.19  4982.7 2284.63  4983.0 2284.13
  4986.5 2284.13  4986.7 2284.63  4994.7 2285.54  5002.2 2286.87  5007.7 2286.87
  5018.2 2288.09  5027.3 2288.43  5033.3 2289.44  5048.3 2289.56  5084.4 2291.84
  5112.9 2293.20  5120.4 2293.93  5126.4 2293.77  5148.9 2294.45  5185.0 2294.82
#Mann=3,-1,0
  4704.7    0.07       0  4982.7    0.05       0  4986.7    0.07       0
Bank Sta=4982.7,4986.7
Exp/Cntr=0.3,0.1

Type RM Length L Ch R = 1,11735,485,485,485
BEGIN DESCRIPTION:
Stream0114 23.0
END DESCRIPTION:
XS GIS Cut Line= 3
      1764125.03     13928125.02      1764425.00     13928325.00
      1764724.98     13928175.01
#Sta/Elev= 30
  4639.4 2291.09  4675.4 2289.11  4711.5 2287.78  4776.1 2286.20  4791.1 2286.22
  4797.1 2285.41  4848.2 2283.31  4869.2 2281.70  4891.7 2280.76  4950.3 2279.04
  4963.9 2278.22  4990.4 2278.15  4990.7 2277.65  4994.2 2277.65  4994.4 2278.15
  4996.9 2278.58  5030.7 2278.75  5058.6 2280.03  5067.0 2281.03  5081.0 2281.27
  5125.7 2284.24  5148.1 2284.71  5156.4 2285.46  5209.5 2287.46  5223.5 2288.41
  5259.9 2289.39  5282.2 2290.68  5299.0 2292.44  5326.9 2293.24  5335.3 2292.70
#Mann=3,-1,0
  4639.4    0.07       0  4990.4    0.05       0  4994.4    0.07       0
Bank Sta=4990.4,4994.4
Exp/Cntr=0.3,0.1

Type RM Length L Ch R = 1,11250,444,444,444
BEGIN DESCRIPTION:
Stream0114 22.0
END DESCRIPTION:
XS GIS Cut Line= 3
      1764124.97     13928674.98      1764325.00     13928775.00
      1764474.96     13928775.00
#Sta/Elev= 30
  4776.0 2276.98  4798.4 2276.06  4806.8 2275.44  4834.7 2274.53  4851.5 2273.40
  4857.1 2273.31  4865.5 2272.55  4873.9 2271.32  4879.5 2271.40  4887.8 2269.48
  4901.8 2267.47  4910.2 2267.70  4918.6 2269.00  4924.2 2268.41  4940.9 2269.72
  4946.5 2269.01  4954.9 2269.32  4977.3 2268.57  4985.7 2267.98  4996.8 2266.65
  5002.1 2266.65  5007.6 2265.05  5007.9 2264.55  5011.4 2264.55  5011.6 2265.05
  5019.6 2265.88  5029.6 2269.57  5039.6 2271.63  5079.6 2274.11  5149.6 2276.89
#Mann=3,-1,0
  4776.0    0.07       0  5007.6    0.05       0  5011.6    0.07       0
Bank Sta=5007.6,5011.6
Exp/Cntr=0.3,0.1

Type RM Length L Ch R = 1,10806,503,503,503
BEGIN DESCRIPTION:
Stream0114 21.0
END DESCRIPTION:
XS GIS Cut Line= 3
      1764025.02     13929075.01      1764175.00     13929125.00
      1764324.99     13929075.00
#Sta/Elev= 30
  4847.7 2270.64  4850.3 2270.64  4868.8 2269.55  4879.3 2269.28  4889.8 2268.80
  4900.4 2268.12  4921.5 2266.95  4932.0 2265.51  4953.1 2263.17  4963.6 2261.39
  4974.2 2259.08  4982.7 2258.85  4983.0 2258.35  4986.5 2258.35  4986.7 2258.85
  5003.2 2259.87  5008.4 2259.87  5016.3 2260.27  5026.9 2261.09  5037.4 2262.05
  5058.5 2264.20  5069.0 2264.93  5079.6 2266.07  5090.1 2266.38  5100.7 2267.47
  5121.7 2269.89  5132.3 2271.42  5142.8 2271.81  5153.4 2271.98  5163.9 2271.82
#Mann=3,-1,0
  4847.7    0.07       0  4982.7    0.05       0  4986.7    0.07       0
Bank Sta=4982.7,4986.7
Exp/Cntr=0.3,0.1

Type RM Length L Ch R = 1,10303,442,442,442
BEGIN DESCRIPTION:
Stream0114 20.0
END DESCRIPTION:
XS GIS Cut Line= 3
      1763925.01     13929725.00      1764175.00     13929625.00
      1764575.04     13929574.99
#Sta/Elev= 30
  4726.7 2273.27  4748.2 2271.27  4771.1 2270.04  4795.3 2267.67  4802.1 2266.19
  4849.2 2260.38  4920.6 2254.78  4927.3 2253.84  4942.1 2253.40  4956.9 2254.00
  4974.4 2253.82  5004.0 2251.57  5004.3 2251.07  5007.8 2251.07  5008.0 2251.57
  5016.1 2252.31  5046.3 2253.18  5066.5 2253.02  5086.6 2251.89  5119.4 2252.59
  5137.0 2252.39  5157.2 2253.70  5187.4 2254.50  5268.0 2260.17  5275.6 2261.82
  5280.6 2261.50  5318.4 2267.30  5338.6 2269.32  5356.2 2272.84  5399.1 2274.97
#Mann=3,-1,0
  4726.7    0.07       0  5004.0    0.05       0  5008.0    0.07       0
Bank Sta=5004,5008
Exp/Cntr=0.3,0.1

Type RM Length L Ch R = 1,9861,428,428,428
BEGIN DESCRIPTION:
Stream0114 19.0
END DESCRIPTION:
XS GIS Cut Line= 3
      1764125.03     13930174.98      1764425.00     13929975.00
      1764625.01     13929724.98
#Sta/Elev= 30
  4639.7 2267.63  4668.2 2264.94  4683.2 2262.11  4704.3 2260.29  4719.3 2258.03
  4755.3 2255.09  4776.4 2254.50  4806.4 2251.67  4812.4 2251.80  4827.5 2249.67
  4833.5 2249.87  4842.5 2248.53  4848.5 2249.45  4856.0 2247.58  4863.5 2247.10
  4941.6 2248.94  4950.6 2248.85  4975.7 2246.84  4975.9 2246.34  4979.7 2246.84
  4986.7 2248.37  5007.4 2249.33  5042.6 2249.52  5071.5 2247.86  5100.3 2248.35
  5141.9 2253.93  5178.7 2257.09  5234.7 2265.69  5292.4 2272.06  5320.4 2274.41
#Mann=3,-1,0
  4639.7    0.07       0  4975.7    0.05       0  4979.7    0.07       0
Bank Sta=4975.7,4979.7
Exp/Cntr=0.3,0.1

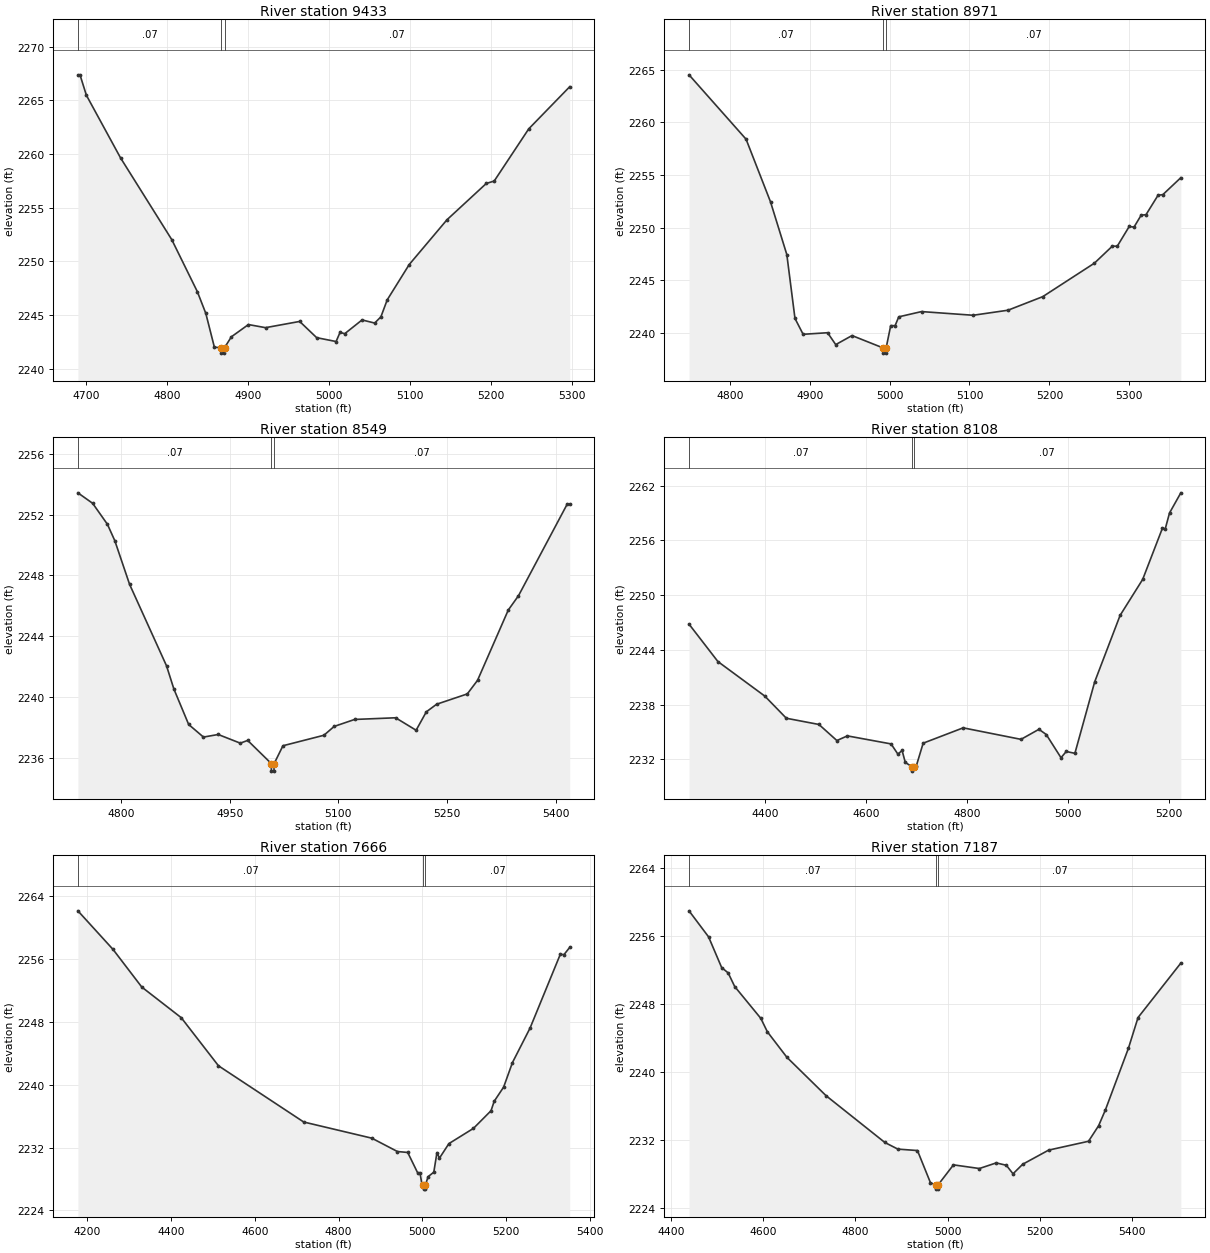
Type RM Length L Ch R = 1,9433,462,462,462
BEGIN DESCRIPTION:
Stream0114 18.0
END DESCRIPTION:
XS GIS Cut Line= 3
      1764175.00     13930425.00      1764475.00     13930325.00
      1764725.02     13930174.99
#Sta/Elev= 30
  4689.6 2267.37  4692.2 2267.37  4700.1 2265.47  4742.3 2259.64  4805.6 2252.03
  4837.2 2247.19  4847.7 2245.16  4858.3 2242.01  4866.8 2241.96  4867.0 2241.46
  4870.5 2241.46  4870.8 2241.96  4879.3 2242.98  4900.4 2244.12  4921.5 2243.83
  4963.7 2244.41  4984.7 2242.90  5008.7 2242.54  5013.6 2243.39  5019.4 2243.27
  5040.8 2244.55  5056.4 2244.26  5064.1 2244.84  5071.9 2246.42  5099.1 2249.71
  5145.8 2253.88  5194.4 2257.26  5204.1 2257.48  5246.8 2262.34  5297.4 2266.26
#Mann=3,-1,0
  4689.6    0.07       0  4866.8    0.05       0  4870.8    0.07       0
Bank Sta=4866.8,4870.8
Exp/Cntr=0.3,0.1

Type RM Length L Ch R = 1,8971,422,422,422
BEGIN DESCRIPTION:
Stream0114 17.0
END DESCRIPTION:
XS GIS Cut Line= 3
      1764225.01     13930775.00      1764475.00     13930725.00
      1764775.00     13930525.00
#Sta/Elev= 30
  4749.0 2264.52  4820.4 2258.40  4851.0 2252.44  4871.4 2247.43  4881.6 2241.36
  4891.8 2239.85  4922.4 2240.00  4932.6 2238.87  4953.0 2239.73  4991.7 2238.56
  4992.0 2238.06  4995.5 2238.06  4995.7 2238.56  5001.4 2240.67  5006.9 2240.67
  5011.5 2241.51  5040.0 2242.01  5104.6 2241.66  5148.2 2242.14  5191.7 2243.43
  5256.3 2246.61  5278.9 2248.24  5284.9 2248.22  5299.9 2250.10  5305.9 2250.04
  5314.9 2251.18  5320.9 2251.22  5336.0 2253.07  5342.0 2253.13  5364.5 2254.74
#Mann=3,-1,0
  4749.0    0.07       0  4991.7    0.05       0  4995.7    0.07       0
Bank Sta=4991.7,4995.7
Exp/Cntr=0.3,0.1

Type RM Length L Ch R = 1,8549,441,441,441
BEGIN DESCRIPTION:
Stream0114 16.0
END DESCRIPTION:
XS GIS Cut Line= 3
      1764325.01     13931025.00      1764575.00     13931075.00
      1764875.00     13930775.00
#Sta/Elev= 30
  4740.3 2253.43  4760.7 2252.74  4781.1 2251.36  4791.3 2250.28  4811.7 2247.41
  4862.7 2242.05  4872.9 2240.52  4893.3 2238.19  4913.7 2237.36  4934.1 2237.53
  4964.6 2236.96  4974.8 2237.14  5007.4 2235.62  5007.6 2235.12  5011.1 2235.12
  5011.4 2235.62  5023.5 2236.79  5080.1 2237.48  5094.2 2238.06  5122.5 2238.52
  5179.1 2238.63  5207.4 2237.81  5221.5 2239.02  5235.7 2239.52  5278.1 2240.20
  5292.2 2241.09  5334.7 2245.72  5348.8 2246.66  5416.0 2252.68  5419.5 2252.68
#Mann=3,-1,0
  4740.3    0.07       0  5007.4    0.05       0  5011.4    0.07       0
Bank Sta=5007.4,5011.4
Exp/Cntr=0.3,0.1

Type RM Length L Ch R = 1,8108,442,442,442
BEGIN DESCRIPTION:
Stream0114 15.0
END DESCRIPTION:
XS GIS Cut Line= 3
      1764325.04     13931724.97      1764925.00     13931275.00
      1765125.04     13931174.98
#Sta/Elev= 30
  4249.5 2246.82  4306.7 2242.72  4399.5 2238.94  4442.2 2236.51  4506.7 2235.83
  4542.2 2234.07  4563.0 2234.58  4649.5 2233.70  4663.0 2232.58  4671.3 2232.98
  4677.6 2231.68  4690.2 2231.22  4690.4 2230.72  4694.2 2231.22  4699.5 2231.30
  4713.0 2233.78  4792.2 2235.46  4906.7 2234.20  4942.2 2235.30  4956.7 2234.73
  4985.9 2232.19  4996.3 2232.87  5013.4 2232.67  5052.6 2240.50  5102.9 2247.78
  5147.6 2251.72  5186.7 2257.33  5192.3 2257.26  5200.7 2258.99  5223.1 2261.20
#Mann=3,-1,0
  4249.5    0.07       0  4690.2    0.05       0  4694.2    0.07       0
Bank Sta=4690.2,4694.2
Exp/Cntr=0.3,0.1

Type RM Length L Ch R = 1,7666,479,479,479
BEGIN DESCRIPTION:
Stream0114 14.0
END DESCRIPTION:
XS GIS Cut Line= 3
      1764074.98     13931825.00      1764875.00     13931675.00
      1765174.98     13931475.01
#Sta/Elev= 30
  4177.3 2262.15  4261.3 2257.23  4329.9 2252.44  4424.1 2248.54  4513.1 2242.41
  4716.6 2235.25  4879.3 2233.19  4940.4 2231.49  4965.0 2231.37  4988.7 2228.78
  4994.3 2228.78  4998.8 2227.36  5002.5 2227.20  5002.8 2226.70  5006.7 2226.70
  5007.0 2227.20  5013.8 2228.29  5027.3 2228.86  5034.8 2231.35  5040.8 2230.65
  5063.4 2232.50  5122.0 2234.44  5164.0 2236.69  5171.5 2237.89  5194.1 2239.70
  5215.1 2242.82  5257.2 2247.22  5329.3 2256.60  5338.3 2256.58  5351.8 2257.49
#Mann=3,-1,0
  4177.3    0.07       0  5002.5    0.05       0  5007.0    0.07       0
Bank Sta=5002.5,5007
Exp/Cntr=0.3,0.1

Type RM Length L Ch R = 1,7187,445,445,445
BEGIN DESCRIPTION:
Stream0114 13.0
END DESCRIPTION:
XS GIS Cut Line= 3
      1764575.01     13932474.99      1764975.00     13932075.00
      1765275.01     13931674.98
#Sta/Elev= 30
  4439.5 2258.95  4481.9 2255.89  4510.2 2252.29  4524.3 2251.66  4538.5 2250.06
  4595.1 2246.32  4609.2 2244.75  4651.6 2241.75  4736.5 2237.24  4863.8 2231.75
  4892.0 2230.97  4934.5 2230.80  4962.7 2227.02  4974.5 2226.77  4974.8 2226.27
  4978.9 2226.27  4979.2 2226.77  5012.5 2229.12  5068.7 2228.69  5105.2 2229.35
  5127.1 2229.07  5141.6 2228.07  5162.5 2229.19  5218.7 2230.85  5305.2 2231.89
  5327.1 2233.72  5341.6 2235.55  5391.6 2242.80  5412.5 2246.42  5505.2 2252.81
#Mann=3,-1,0
  4439.5    0.07       0  4974.5    0.05       0  4979.2    0.07       0
Bank Sta=4974.5,4979.2
Exp/Cntr=0.3,0.1

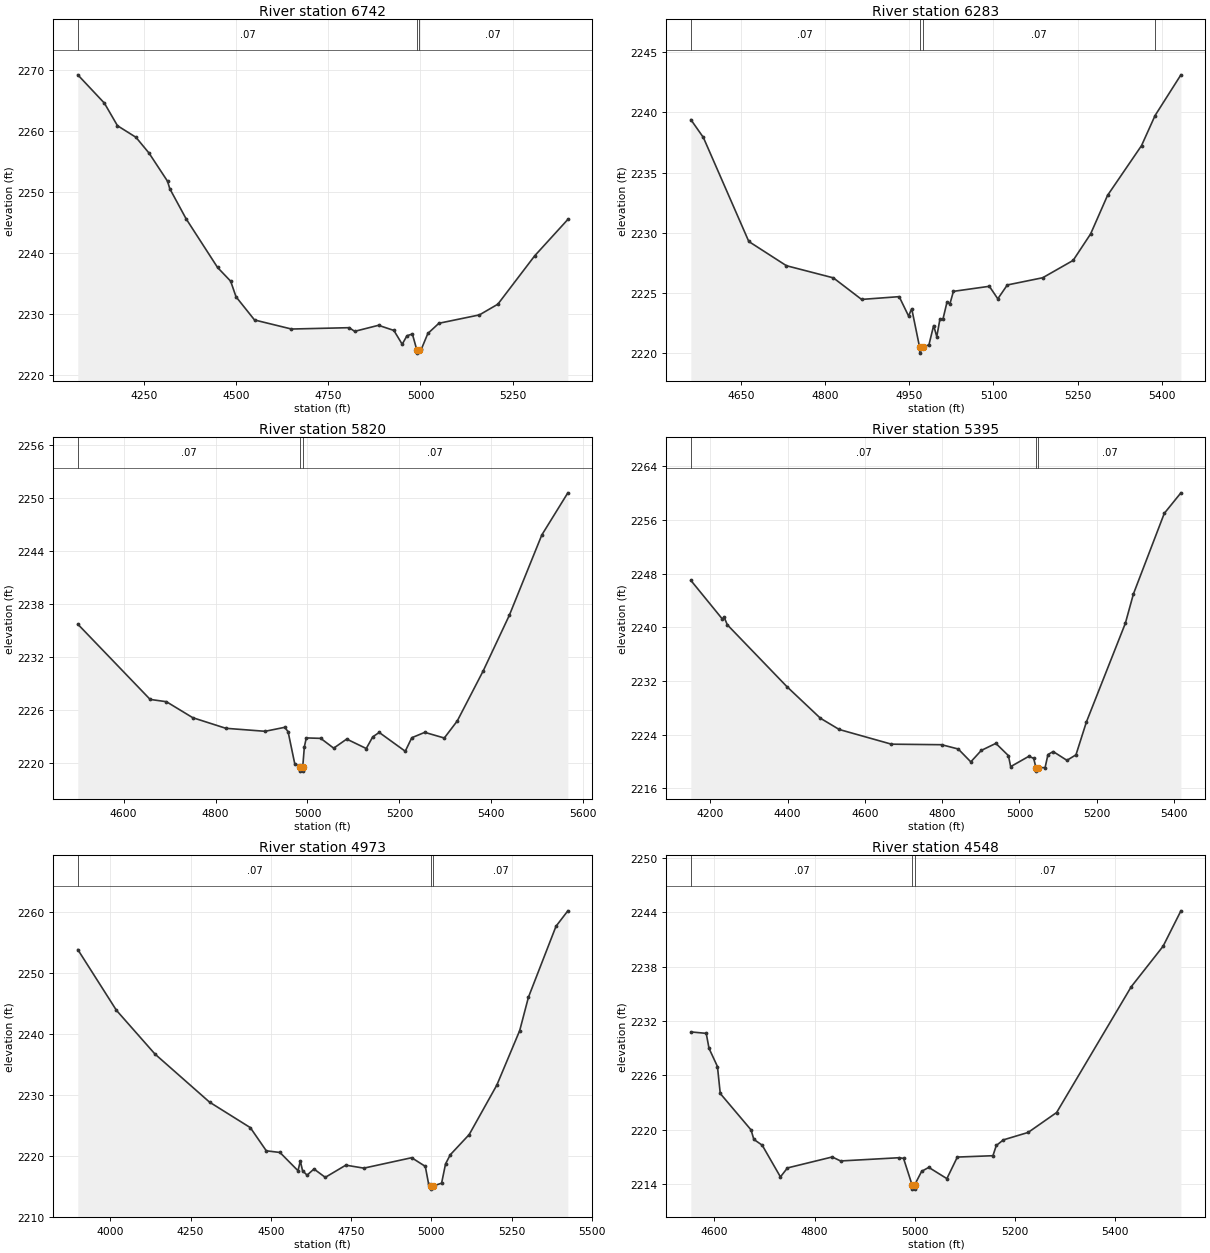
Type RM Length L Ch R = 1,6742,459,459,459
BEGIN DESCRIPTION:
Stream0114 12.0
END DESCRIPTION:
XS GIS Cut Line= 3
      1764574.99     13932725.01      1765325.00     13932175.00
      1765325.00     13931774.97
#Sta/Elev= 30
  4069.9 2269.13  4142.1 2264.50  4177.6 2260.81  4227.7 2258.92  4263.3 2256.33
  4313.4 2251.74  4319.6 2250.51  4363.6 2245.62  4449.3 2237.63  4484.8 2235.39
  4499.4 2232.84  4549.6 2229.05  4649.9 2227.57  4806.6 2227.79  4821.3 2227.19
  4886.1 2228.18  4927.8 2227.34  4950.4 2225.08  4963.3 2226.47  4978.0 2226.76
  4990.2 2224.13  4990.6 2223.63  4995.0 2224.13  5002.5 2224.30  5020.0 2226.84
  5050.0 2228.51  5160.0 2229.88  5210.0 2231.63  5310.0 2239.54  5400.0 2245.49
#Mann=3,-1,0
  4069.9    0.07       0  4990.2    0.05       0  4995.0    0.07       0
Bank Sta=4990.2,4995
Exp/Cntr=0.3,0.1

Type RM Length L Ch R = 1,6283,463,463,463
BEGIN DESCRIPTION:
Stream0114 11.0
END DESCRIPTION:
XS GIS Cut Line= 3
      1764975.04     13932774.98      1765375.00     13932575.00
      1765775.03     13932424.99
#Sta/Elev= 30
  4560.0 2239.40  4582.3 2237.92  4663.4 2229.28  4730.5 2227.27  4814.3 2226.26
  4864.6 2224.47  4931.7 2224.70  4948.5 2223.09  4954.1 2223.70  4968.1 2220.51
  4968.5 2220.01  4973.6 2220.51  4984.8 2220.70  4993.2 2222.30  4998.8 2221.38
  5004.4 2222.83  5009.8 2222.83  5017.0 2224.24  5022.3 2224.11  5028.5 2225.14
  5092.6 2225.56  5107.7 2224.52  5124.6 2225.67  5187.8 2226.27  5242.1 2227.71
  5273.3 2229.91  5303.5 2233.11  5364.1 2237.24  5388.3 2239.74  5434.4 2243.12
#Mann=4,-1,0
  4560.0    0.07       0  4968.1    0.05       0  4973.6    0.07       0
  5388.3     0.1       0
Bank Sta=4968.1,4973.6
Exp/Cntr=0.3,0.1

Type RM Length L Ch R = 1,5820,425,425,425
BEGIN DESCRIPTION:
Stream0114 10.0
END DESCRIPTION:
XS GIS Cut Line= 3
      1765075.02     13933274.99      1765475.00     13932975.00
      1765875.03     13932574.97
#Sta/Elev= 30
  4500.5 2235.69  4657.8 2227.17  4693.2 2226.91  4750.5 2225.10  4822.4 2223.90
  4907.8 2223.56  4950.5 2224.01  4957.8 2223.52  4972.4 2219.86  4984.2 2219.55
  4984.6 2219.05  4989.2 2219.05  4989.7 2219.55  4993.2 2221.80  4997.4 2222.81
  5028.8 2222.76  5057.0 2221.65  5085.3 2222.68  5127.8 2221.61  5141.9 2222.93
  5156.0 2223.43  5212.6 2221.30  5226.8 2222.83  5255.0 2223.44  5297.5 2222.80
  5325.7 2224.73  5382.3 2230.42  5438.9 2236.69  5509.6 2245.79  5566.2 2250.56
#Mann=3,-1,0
  4500.5    0.07       0  4984.2    0.05       0  4989.7    0.07       0
Bank Sta=4984.2,4989.7
Exp/Cntr=0.3,0.1

Type RM Length L Ch R = 1,5395,422,422,422
BEGIN DESCRIPTION:
Stream0114 9.0
END DESCRIPTION:
XS GIS Cut Line= 3
      1764925.00     13933375.00      1765725.00     13933125.00
      1766075.03     13932874.98
#Sta/Elev= 30
  4149.5 2247.00  4230.7 2241.26  4235.9 2241.48  4243.8 2240.38  4398.3 2231.14
  4484.8 2226.44  4533.5 2224.76  4668.6 2222.57  4798.5 2222.49  4841.5 2221.85
  4874.0 2219.93  4901.2 2221.64  4938.9 2222.69  4971.4 2220.86  4977.2 2219.22
  5024.5 2220.77  5036.8 2220.45  5042.7 2219.05  5043.1 2218.55  5048.2 2219.05
  5066.3 2219.08  5073.7 2221.02  5087.2 2221.47  5122.8 2220.16  5146.2 2220.98
  5173.2 2225.88  5274.0 2240.60  5294.9 2244.98  5374.8 2257.00  5417.8 2260.06
#Mann=3,-1,0
  4149.5    0.07       0  5042.7    0.05       0  5048.2    0.07       0
Bank Sta=5042.7,5048.2
Exp/Cntr=0.3,0.1

Type RM Length L Ch R = 1,4973,425,425,425
BEGIN DESCRIPTION:
Stream0114 8.0
END DESCRIPTION:
XS GIS Cut Line= 3
      1765225.03     13934224.97      1765975.00     13933425.00
      1766325.03     13933174.98
#Sta/Elev= 30
  3898.7 2253.78  4019.1 2243.82  4139.2 2236.65  4309.2 2228.77  4436.2 2224.59
  4486.0 2220.79  4528.5 2220.52  4584.7 2217.53  4592.0 2219.12  4598.9 2217.53
  4613.0 2216.80  4634.5 2217.81  4669.7 2216.44  4733.7 2218.44  4789.9 2217.95
  4938.8 2219.66  4981.3 2218.24  4991.8 2215.30  4999.8 2215.01  5000.3 2214.51
  5005.4 2215.01  5032.1 2215.49  5044.4 2218.65  5059.1 2220.14  5118.1 2223.46
  5204.2 2231.57  5275.4 2240.50  5302.5 2245.95  5388.5 2257.60  5425.4 2260.13
#Mann=3,-1,0
  3898.7    0.07       0  4999.8    0.05       0  5005.4    0.07       0
Bank Sta=4999.8,5005.4
Exp/Cntr=0.3,0.1

Type RM Length L Ch R = 1,4548,430,430,430
BEGIN DESCRIPTION:
Stream0114 7.0
END DESCRIPTION:
XS GIS Cut Line= 3
      1765725.01     13933975.00      1766125.00     13933775.00
      1766474.99     13933375.01
#Sta/Elev= 30
  4552.9 2230.80  4583.6 2230.64  4589.2 2228.98  4606.0 2226.98  4611.6 2224.00
  4673.1 2219.98  4678.7 2218.93  4695.4 2218.29  4731.8 2214.79  4745.8 2215.78
  4835.2 2216.99  4852.0 2216.55  4969.4 2216.91  4977.7 2216.83  4994.5 2213.94
  4995.0 2213.44  4999.7 2213.44  5000.1 2213.94  5013.9 2215.41  5028.1 2215.84
  5064.2 2214.60  5085.1 2216.98  5156.2 2217.13  5162.9 2218.26  5177.1 2218.88
  5226.5 2219.70  5283.4 2221.90  5432.4 2235.79  5496.0 2240.26  5531.6 2244.17
#Mann=3,-1,0
  4552.9    0.07       0  4994.5    0.05       0  5000.1    0.07       0
Bank Sta=4994.5,5000.1
Exp/Cntr=0.3,0.1

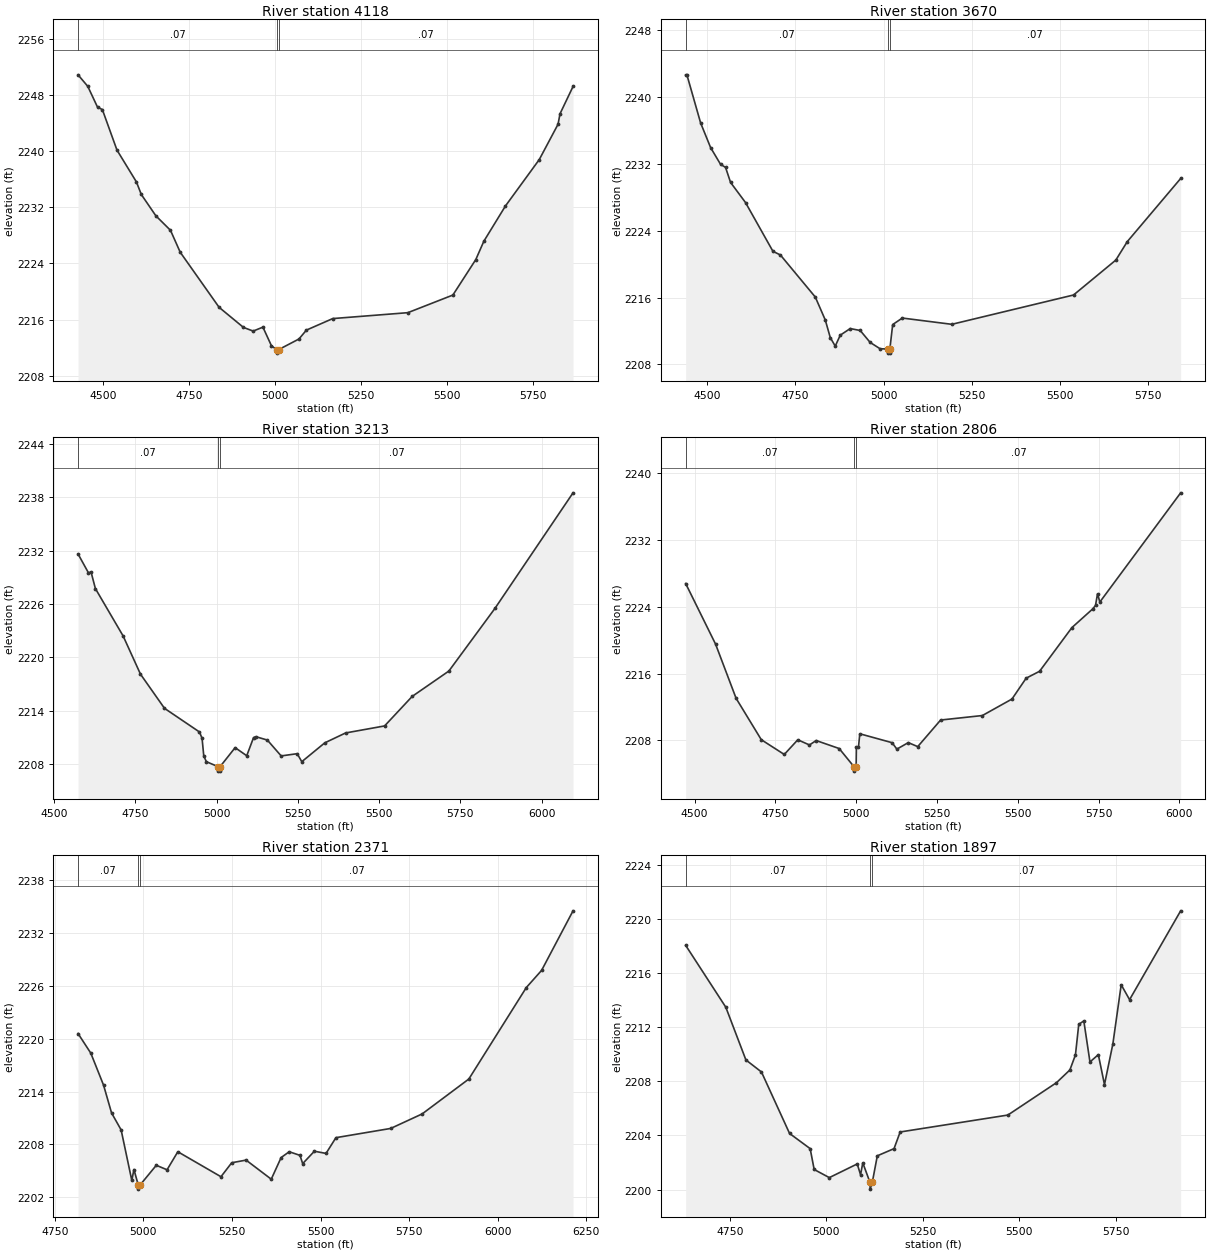
Type RM Length L Ch R = 1,4118,448,448,448
BEGIN DESCRIPTION:
Stream0114 6.0
END DESCRIPTION:
XS GIS Cut Line= 3
      1765824.98     13934575.02      1766225.00     13934175.00
      1766574.99     13933375.02
#Sta/Elev= 30
  4428.3 2250.85  4456.6 2249.21  4484.9 2246.25  4499.0 2245.90  4541.5 2240.13
  4598.0 2235.60  4612.2 2233.81  4654.6 2230.77  4697.0 2228.71  4725.3 2225.59
  4838.4 2217.74  4909.2 2214.88  4937.4 2214.36  4965.7 2214.92  4990.5 2212.27
  5005.5 2211.72  5006.0 2211.22  5011.4 2211.72  5070.4 2213.23  5092.2 2214.50
  5168.7 2216.14  5387.0 2216.98  5517.9 2219.49  5584.6 2224.55  5608.0 2227.16
  5670.8 2232.18  5769.0 2238.78  5823.6 2243.81  5829.4 2245.31  5867.2 2249.19
#Mann=3,-1,0
  4428.3    0.07       0  5005.5    0.05       0  5011.4    0.07       0
Bank Sta=5005.5,5011.4
Exp/Cntr=0.3,0.1

Type RM Length L Ch R = 1,3670,457,457,457
BEGIN DESCRIPTION:
Stream0114 5.0
END DESCRIPTION:
XS GIS Cut Line= 3
      1766125.02     13934874.98      1766525.00     13934475.00
      1766775.00     13933675.01
#Sta/Elev= 30
  4438.6 2242.67  4442.1 2242.67  4481.0 2236.91  4509.3 2233.96  4537.6 2231.95
  4551.7 2231.59  4565.9 2229.79  4608.3 2227.38  4686.1 2221.54  4707.3 2221.10
  4806.3 2216.06  4834.6 2213.31  4848.7 2211.21  4862.8 2210.19  4877.0 2211.50
  4905.3 2212.29  4933.6 2212.06  4961.8 2210.63  4990.1 2209.87  5011.8 2209.85
  5012.3 2209.35  5017.2 2209.35  5017.7 2209.85  5025.7 2212.77  5053.0 2213.55
  5193.4 2212.80  5538.6 2216.31  5658.5 2220.49  5691.0 2222.70  5842.4 2230.26
#Mann=3,-1,0
  4438.6    0.07       0  5011.8    0.05       0  5017.7    0.07       0
Bank Sta=5011.8,5017.7
Exp/Cntr=0.3,0.1

Type RM Length L Ch R = 1,3213,407,407,407
BEGIN DESCRIPTION:
Stream0114 4.0
END DESCRIPTION:
XS GIS Cut Line= 3
      1766275.01     13935024.99      1766675.00     13934875.00
      1767475.02     13934124.98
#Sta/Elev= 30
  4573.2 2231.62  4605.2 2229.50  4613.2 2229.60  4626.6 2227.73  4712.0 2222.40
  4765.4 2218.11  4839.3 2214.27  4947.0 2211.61  4955.0 2210.90  4960.3 2208.90
  4968.3 2208.27  5004.5 2207.71  5005.0 2207.21  5010.0 2207.21  5010.4 2207.71
  5056.8 2209.85  5092.5 2208.94  5113.5 2210.98  5120.8 2211.08  5156.0 2210.70
  5198.5 2208.92  5247.8 2209.17  5262.0 2208.27  5332.8 2210.39  5396.8 2211.50
  5516.9 2212.29  5601.9 2215.61  5714.8 2218.46  5856.4 2225.49  6097.0 2238.49
#Mann=3,-1,0
  4573.2    0.07       0  5004.5    0.05       0  5010.4    0.07       0
Bank Sta=5004.5,5010.4
Exp/Cntr=0.3,0.1

Type RM Length L Ch R = 1,2806,435,435,435
BEGIN DESCRIPTION:
Stream0114 3.0
END DESCRIPTION:
XS GIS Cut Line= 3
      1766575.00     13935375.00      1766975.00     13935025.00
      1767575.00     13934225.00
#Sta/Elev= 30
  4472.5 2226.80  4565.0 2219.53  4628.6 2213.02  4706.5 2208.06  4777.6 2206.29
  4819.4 2208.05  4855.5 2207.43  4876.3 2207.96  4947.5 2207.00  4993.9 2204.79
  4994.4 2204.29  4999.9 2204.79  5000.7 2207.15  5007.1 2207.15  5011.3 2208.77
  5111.3 2207.70  5125.9 2206.93  5161.3 2207.71  5190.5 2207.23  5261.3 2210.42
  5390.5 2210.96  5482.1 2212.94  5525.9 2215.44  5567.5 2216.27  5667.5 2221.51
  5732.1 2223.76  5740.5 2224.17  5746.7 2225.56  5754.0 2224.58  6004.0 2237.68
#Mann=3,-1,0
  4472.5    0.07       0  4993.9    0.05       0  4999.9    0.07       0
Bank Sta=4993.9,4999.9
Exp/Cntr=0.3,0.1

Type RM Length L Ch R = 1,2371,474,474,474
BEGIN DESCRIPTION:
Stream0114 2.0
END DESCRIPTION:
XS GIS Cut Line= 3
      1766725.04     13935524.97      1766875.00     13935425.00
      1768075.02     13935225.00
#Sta/Elev= 30
  4815.5 2220.60  4851.5 2218.37  4887.6 2214.72  4910.1 2211.57  4937.1 2209.64
  4967.2 2203.90  4973.2 2205.14  4985.2 2203.41  4985.7 2202.91  4991.2 2203.41
  5036.3 2205.62  5066.7 2205.11  5097.1 2207.16  5218.8 2204.32  5249.2 2205.91
  5289.7 2206.21  5360.7 2204.04  5388.6 2206.50  5411.4 2207.16  5441.8 2206.75
  5449.4 2205.81  5482.4 2207.22  5515.3 2206.97  5543.2 2208.76  5697.8 2209.81
  5786.5 2211.46  5918.3 2215.43  6080.5 2225.83  6123.6 2227.78  6212.3 2234.55
#Mann=3,-1,0
  4815.5    0.07       0  4985.2    0.05       0  4991.2    0.07       0
Bank Sta=4985.2,4991.2
Exp/Cntr=0.3,0.1

Type RM Length L Ch R = 1,1897,758,758,758
BEGIN DESCRIPTION:
Stream0114 1.0
END DESCRIPTION:
XS GIS Cut Line= 3
      1766725.01     13935725.00      1767075.00     13935825.00
      1767875.02     13935374.99
#Sta/Elev= 30
  4636.0 2218.04  4740.0 2213.47  4792.0 2209.58  4832.3 2208.69  4905.1 2204.15
  4958.4 2203.03  4968.8 2201.49  5008.0 2200.89  5080.3 2201.90  5088.9 2201.10
  5094.7 2201.98  5113.3 2200.54  5113.8 2200.04  5119.3 2200.54  5132.3 2202.50
  5175.6 2203.03  5191.5 2204.26  5470.4 2205.51  5596.3 2207.90  5631.0 2208.84
  5645.4 2209.95  5654.0 2212.21  5667.1 2212.46  5683.0 2209.43  5704.7 2209.97
  5720.6 2207.76  5742.3 2210.76  5763.9 2215.13  5785.6 2214.03  5917.9 2220.59
#Mann=3,-1,0
  4636.0    0.07       0  5113.3    0.05       0  5119.3    0.07       0
Bank Sta=5113.3,5119.3
Exp/Cntr=0.3,0.1

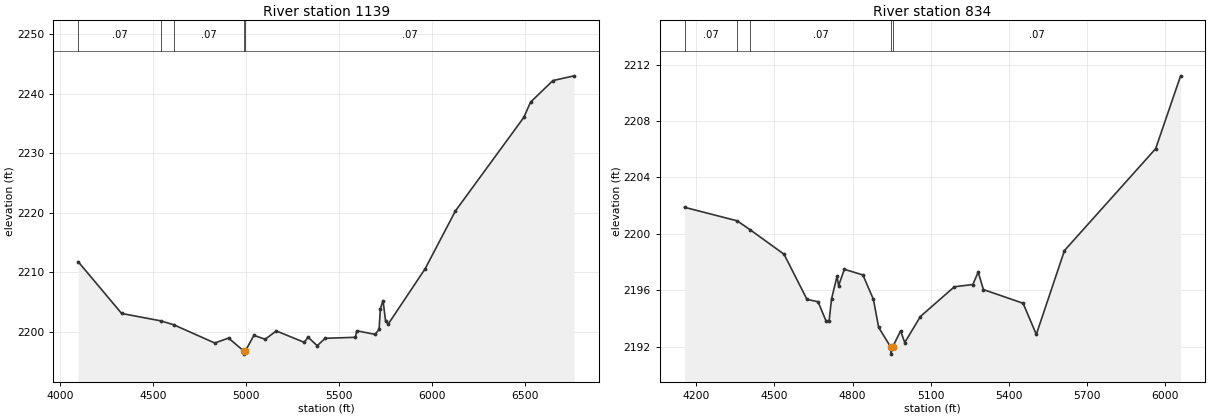
Type RM Length L Ch R = 1,1139,305,305,305
BEGIN DESCRIPTION:
Stream0114 0.0
END DESCRIPTION:
XS GIS Cut Line= 4
      1766680.14     13935927.53      1767051.58     13936498.23
      1767641.33     13936459.78      1768596.98     13935445.36
#Sta/Elev= 30
  4096.8 2211.77  4330.7 2203.05  4541.6 2201.80  4610.4 2201.15  4831.3 2198.08
  4905.3 2198.91  4988.0 2196.71  4988.5 2196.21  4995.2 2196.71  5041.7 2199.37
  5101.8 2198.71  5162.0 2200.11  5312.3 2198.19  5332.3 2199.07  5381.8 2197.62
  5424.3 2198.87  5586.9 2199.04  5594.2 2200.14  5692.9 2199.53  5714.3 2200.39
  5721.2 2203.86  5735.4 2205.22  5749.5 2201.70  5763.7 2201.28  5961.9 2210.58
  6124.6 2220.30  6492.4 2236.04  6528.0 2238.58  6648.1 2242.21  6762.4 2243.01
#Mann=5,-1,0
  4096.8    0.07       0  4541.6   0.035       0  4610.4    0.07       0
  4988.0    0.05       0  4995.2    0.07       0
Bank Sta=4988,4995.2
Exp/Cntr=0.3,0.1

Type RM Length L Ch R = 1,834,0,0,0
BEGIN DESCRIPTION:
Stream0114 0.1
END DESCRIPTION:
XS GIS Cut Line= 4
      1766737.22     13936245.53      1767087.53     13936802.29
      1767451.80     13936776.07      1768320.86     13936622.69
#Sta/Elev= 30
  4154.7 2201.88  4356.7 2200.92  4407.9 2200.27  4536.8 2198.55  4625.1 2195.34
  4667.5 2195.18  4697.6 2193.84  4709.9 2193.81  4719.3 2195.38  4740.5 2196.99
  4746.4 2196.31  4768.4 2197.48  4839.7 2197.08  4880.1 2195.35  4900.2 2193.36
  4946.7 2191.96  4947.2 2191.46  4953.9 2191.96  4984.6 2193.11  5000.5 2192.28
  5060.6 2194.13  5191.1 2196.24  5262.2 2196.40  5282.5 2197.28  5302.8 2196.04
  5455.1 2195.07  5505.9 2192.86  5614.0 2198.81  5964.3 2206.04  6060.2 2211.21
#Mann=5,-1,0
  4154.7    0.07       0  4356.7   0.035       0  4407.9    0.07       0
  4946.7    0.05       0  4953.9    0.07       0
Bank Sta=4946.7,4953.9
Exp/Cntr=0.3,0.1

Chan Stop Cuts=-1