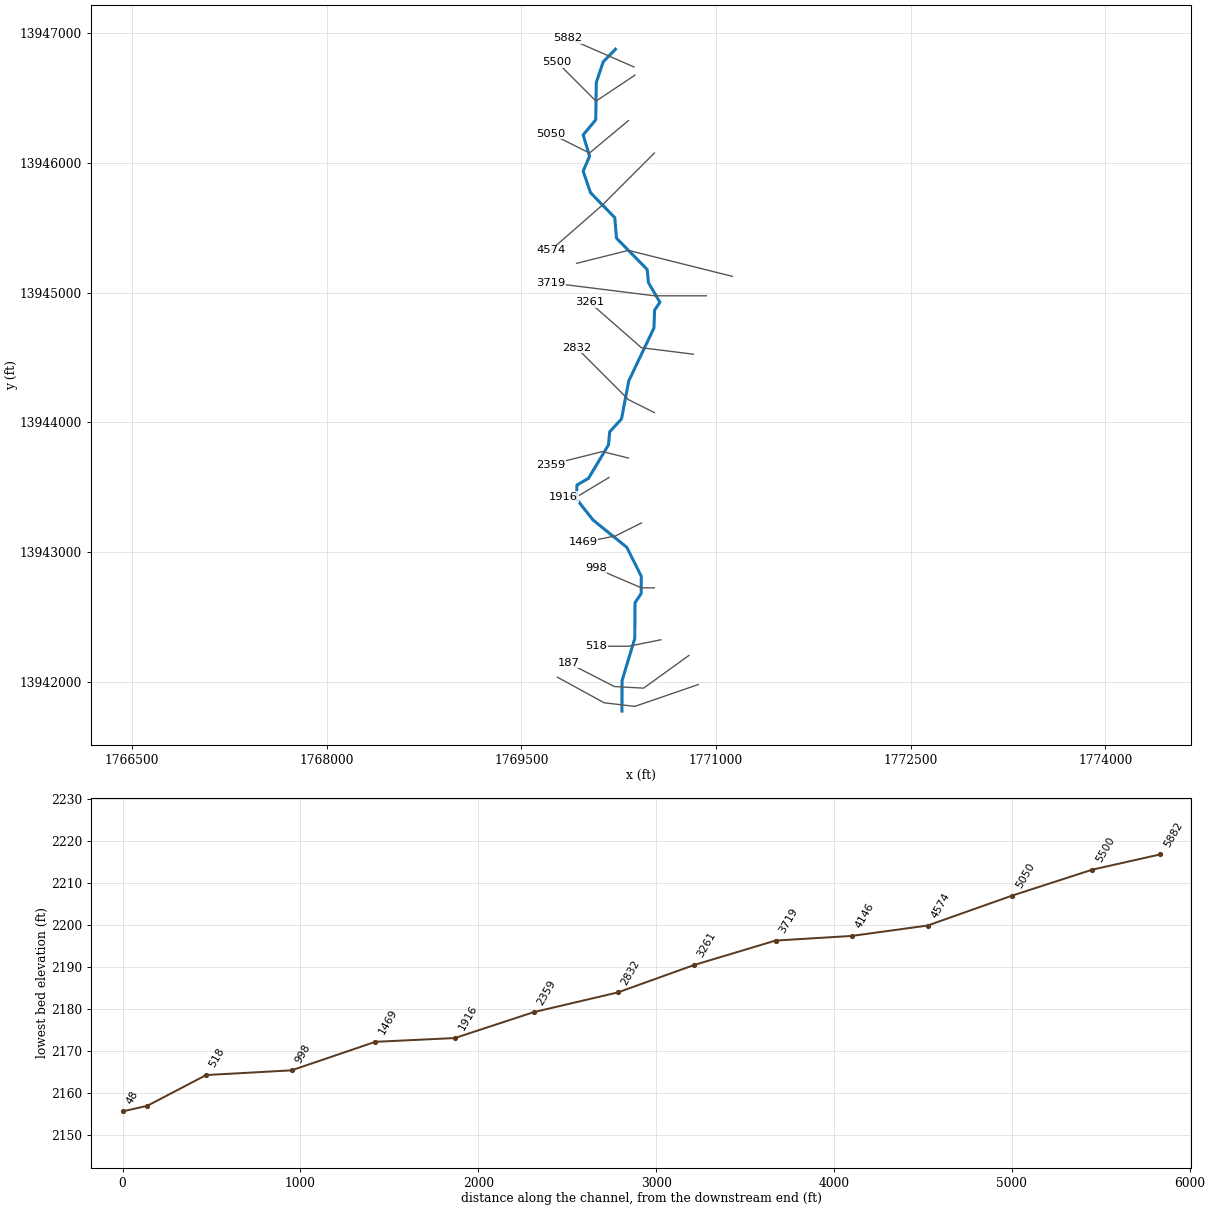
--- Stream0116.prj (project) ---

Proj Title=Stream0116 Base Level Engineering
Current Plan=p01
Default Exp/Contr=0.3,0.1
English Units
Geom File=g01
Flow File=f01
Plan File=p01
BEGIN DESCRIPTION:
Stream0116
END DESCRIPTION:

--- Stream0116.p01 (plan) ---

Plan Title=Multiple Run
Short Identifier=Multiple
Geom File=g01
Flow File=f01
Subcritical Flow
K Sum by GR= 0
Std Step Tol= 0.01
Critical Tol= 0.01
Num of Std Step Trials= 20
Max Error Tol= 0.3
Flow Tol Ratio= 0.001
Split Flow NTrial= 30
Split Flow Tol= 0.02
Split Flow Ratio= 0.02
Log Output Level= 0
Friction Slope Method= 1
Unsteady Friction Slope Method= 2
Unsteady Bridges Friction Slope Method= 1
Parabolic Critical Depth
Global Vel Dist=  1 , 1 , 1
Global Log Level= 0
CheckData=True
Encroach Param= -1, 0, 0, 0
BEGIN DESCRIPTION:
Multiple Run
END DESCRIPTION:

--- Stream0116.f01 (steady flow) ---

Flow Title=Multiple
Number of Profiles=7
Profile Names=10-year,25-year,50-year,1pct_min,100-year,1pct_plu,500-year
River Rch & RM= Stream0116,Reach-1,5882
    1168    2005    2805    1894    3778    7539    6783
River Rch & RM= Stream0116,Reach-1,4574
    1484    2579    3634    2470    4928    9832    8967
Boundary for River Rch & Prof#=Stream0116,Reach-1,1
Up Type=0
Dn Type=3
Dn Slope=0.005
Boundary for River Rch & Prof#=Stream0116,Reach-1,2
Up Type=0
Dn Type=3
Dn Slope=0.005
Boundary for River Rch & Prof#=Stream0116,Reach-1,3
Up Type=0
Dn Type=3
Dn Slope=0.005
Boundary for River Rch & Prof#=Stream0116,Reach-1,4
Up Type=0
Dn Type=3
Dn Slope=0.005
Boundary for River Rch & Prof#=Stream0116,Reach-1,5
Up Type=0
Dn Type=3
Dn Slope=0.005
Boundary for River Rch & Prof#=Stream0116,Reach-1,6
Up Type=0
Dn Type=3
Dn Slope=0.005
Boundary for River Rch & Prof#=Stream0116,Reach-1,7
Up Type=0
Dn Type=3
Dn Slope=0.005

--- Stream0116.g01 (geometry) ---

Geom Title=Existing Conditions

River Reach=Stream0116,Reach-1
Reach XY= 30
      1770225.00     13946875.00      1770130.46     13946777.45
      1770077.26     13946619.06      1770072.93     13946330.86
      1769975.94     13946214.52      1770025.39     13946050.00
      1769975.77     13945935.69      1770032.86     13945768.83
      1770219.53     13945577.45      1770232.82     13945418.81
      1770469.48     13945177.43      1770478.83     13945076.59
      1770567.47     13944925.01      1770526.40     13944864.56
      1770521.24     13944726.56      1770327.27     13944319.06
      1770271.38     13944026.50      1770180.54     13943927.42
      1770171.17     13943826.59      1770016.91     13943568.69
      1769928.08     13943516.69      1769924.45     13943409.85
      1770051.53     13943248.01      1770311.38     13943038.21
      1770423.81     13942814.50      1770422.75     13942680.94
      1770375.52     13942609.78      1770373.78     13942335.50
      1770275.52     13942009.78      1770275.00     13941775.00

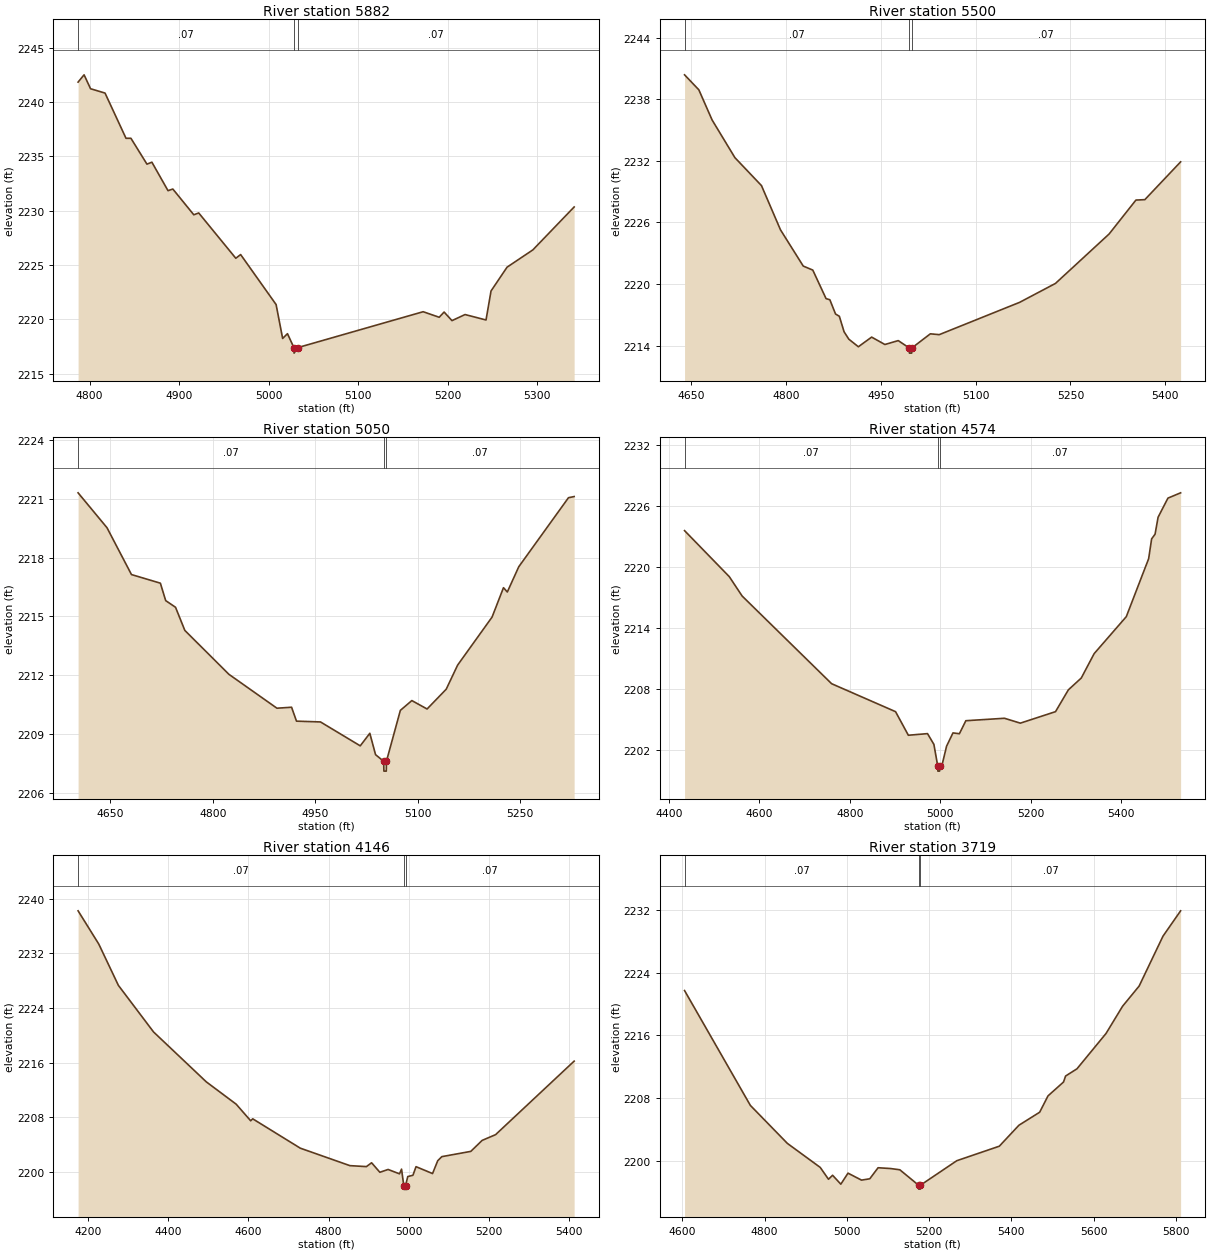
Type RM Length L Ch R = 1,5882,382,382,382
BEGIN DESCRIPTION:
Stream0116 13.0
END DESCRIPTION:
XS GIS Cut Line= 2
      1770367.73     13946738.03      1769859.97     13946959.36
#Sta/Elev= 30
  4787.1 2241.84  4793.8 2242.51  4801.0 2241.23  4817.2 2240.83  4840.6 2236.67
  4846.1 2236.67  4864.0 2234.29  4869.5 2234.47  4887.5 2231.85  4892.9 2232.00
  4916.3 2229.63  4921.8 2229.80  4963.2 2225.63  4968.6 2225.97  5008.2 2221.37
  5015.5 2218.25  5020.9 2218.69  5028.1 2217.40  5028.3 2216.90  5032.1 2217.40
  5172.4 2220.71  5190.3 2220.20  5195.8 2220.68  5204.6 2219.89  5219.2 2220.45
  5242.6 2219.95  5248.2 2222.62  5266.1 2224.81  5294.9 2226.40  5341.0 2230.35
#Mann=3,-1,0
  4787.1    0.07       0  5028.1    0.05       0  5032.1    0.07       0
Bank Sta=5028.1,5032.1
Exp/Cntr=0.3,0.1

Type RM Length L Ch R = 1,5500,450,450,450
BEGIN DESCRIPTION:
Stream0116 12.0
END DESCRIPTION:
XS GIS Cut Line= 3
      1770375.04     13946675.03      1770075.00     13946475.00
      1769774.98     13946775.02
#Sta/Elev= 30
  4639.4 2240.38  4662.0 2238.92  4683.0 2235.98  4719.1 2232.31  4761.1 2229.59
  4791.2 2225.28  4827.2 2221.75  4842.3 2221.36  4863.3 2218.58  4869.3 2218.47
  4878.3 2217.08  4884.3 2216.86  4891.8 2215.35  4899.3 2214.63  4914.4 2213.89
  4935.4 2214.83  4956.4 2214.11  4977.5 2214.49  4995.0 2213.77  4995.2 2213.27
  4998.7 2213.27  4999.0 2213.77  5028.3 2215.15  5042.4 2215.07  5169.7 2218.22
  5226.3 2220.06  5311.1 2224.87  5353.6 2228.18  5367.7 2228.22  5424.3 2231.90
#Mann=3,-1,0
  4639.4    0.07       0  4995.0    0.05       0  4999.0    0.07       0
Bank Sta=4995,4999
Exp/Cntr=0.3,0.1

Type RM Length L Ch R = 1,5050,476,476,476
BEGIN DESCRIPTION:
Stream0116 11.0
END DESCRIPTION:
XS GIS Cut Line= 3
      1770325.01     13946325.01      1770025.00     13946075.00
      1769725.04     13946224.98
#Sta/Elev= 30
  4602.9 2221.30  4645.2 2219.52  4681.0 2217.13  4723.3 2216.69  4731.1 2215.80
  4745.5 2215.46  4759.1 2214.28  4823.6 2212.04  4893.9 2210.31  4915.3 2210.36
  4922.5 2209.65  4957.6 2209.61  5015.8 2208.39  5029.8 2209.03  5038.2 2207.94
  5050.1 2207.60  5050.4 2207.10  5053.9 2207.10  5054.1 2207.60  5074.5 2210.20
  5091.3 2210.70  5113.6 2210.27  5141.6 2211.28  5158.3 2212.51  5208.7 2214.96
  5225.4 2216.46  5231.0 2216.24  5247.8 2217.53  5320.5 2221.05  5328.8 2221.11
#Mann=3,-1,0
  4602.9    0.07       0  5050.1    0.05       0  5054.1    0.07       0
Bank Sta=5050.1,5054.1
Exp/Cntr=0.3,0.1

Type RM Length L Ch R = 1,4574,428,428,428
BEGIN DESCRIPTION:
Stream0116 10.0
END DESCRIPTION:
XS GIS Cut Line= 3
      1770525.00     13946075.00      1770125.00     13945675.00
      1769725.00     13945325.00
#Sta/Elev= 30
  4434.3 2223.62  4533.3 2219.09  4561.6 2217.19  4759.6 2208.56  4901.0 2205.81
  4929.3 2203.49  4971.7 2203.65  4985.8 2202.59  4994.3 2200.46  4994.6 2199.96
  4998.3 2199.96  4998.6 2200.46  5003.3 2200.46  5013.8 2202.41  5028.0 2203.72
  5042.2 2203.64  5056.5 2204.92  5141.9 2205.16  5177.0 2204.68  5254.8 2205.81
  5283.3 2207.96  5311.8 2209.12  5340.3 2211.52  5411.4 2215.16  5460.8 2220.86
  5467.4 2222.81  5475.0 2223.27  5481.7 2224.94  5503.5 2226.82  5531.5 2227.34
#Mann=3,-1,0
  4434.3    0.07       0  4994.3    0.05       0  4998.6    0.07       0
Bank Sta=4994.3,4998.6
Exp/Cntr=0.3,0.1

Type RM Length L Ch R = 1,4146,427,427,427
BEGIN DESCRIPTION:
Stream0116 9.0
END DESCRIPTION:
XS GIS Cut Line= 3
      1771125.03     13945124.99      1770325.00     13945325.00
      1769924.96     13945224.99
#Sta/Elev= 30
  4175.3 2238.25  4226.9 2233.38  4275.8 2227.33  4363.4 2220.51  4494.9 2213.20
  4569.6 2209.92  4605.7 2207.49  4610.8 2207.78  4729.4 2203.48  4853.1 2200.92
  4894.3 2200.78  4907.2 2201.34  4927.8 2199.95  4948.4 2200.36  4976.8 2199.72
  4981.9 2200.41  4987.5 2197.98  4987.8 2197.48  4991.5 2197.48  4991.8 2197.98
  4997.4 2199.32  5010.3 2199.51  5018.0 2200.77  5059.2 2199.76  5072.1 2201.64
  5082.4 2202.24  5154.6 2203.01  5182.9 2204.62  5216.4 2205.46  5412.3 2216.23
#Mann=3,-1,0
  4175.3    0.07       0  4987.5    0.05       0  4991.8    0.07       0
Bank Sta=4987.5,4991.8
Exp/Cntr=0.3,0.1

Type RM Length L Ch R = 1,3719,458,458,458
BEGIN DESCRIPTION:
Stream0116 8.0
END DESCRIPTION:
XS GIS Cut Line= 3
      1770925.04     13944975.00      1770525.00     13944975.00
      1769724.97     13945075.00
#Sta/Elev= 30
  4605.2 2221.73  4765.2 2207.07  4855.2 2202.22  4935.2 2199.15  4955.2 2197.64
  4965.2 2198.15  4985.2 2197.01  5002.7 2198.42  5035.5 2197.53  5055.6 2197.70
  5075.8 2199.11  5106.0 2199.01  5128.7 2198.85  5174.3 2196.88  5174.6 2196.38
  5178.5 2196.38  5178.8 2196.88  5267.3 2200.01  5370.6 2201.86  5418.4 2204.54
  5468.8 2206.20  5489.0 2208.28  5526.8 2210.06  5531.8 2210.82  5559.5 2211.74
  5630.1 2216.25  5670.4 2219.73  5710.7 2222.31  5768.6 2228.67  5811.5 2231.91
#Mann=3,-1,0
  4605.2    0.07       0  5174.3    0.05       0  5178.8    0.07       0
Bank Sta=5174.3,5178.8
Exp/Cntr=0.3,0.1

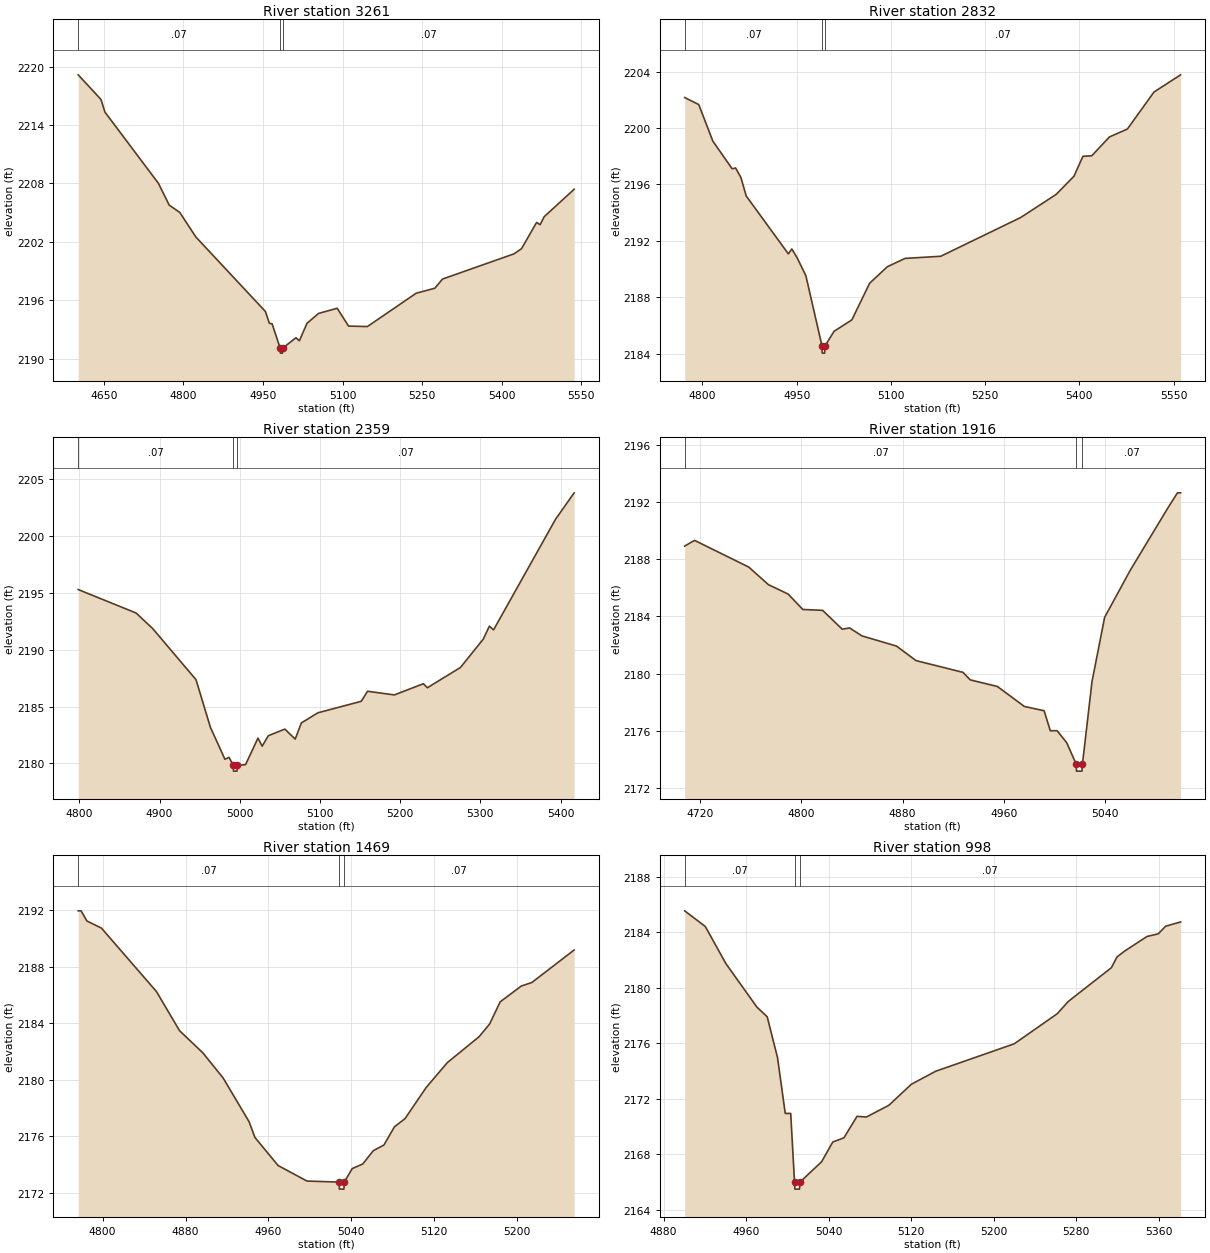
Type RM Length L Ch R = 1,3261,429,429,429
BEGIN DESCRIPTION:
Stream0116 7.0
END DESCRIPTION:
XS GIS Cut Line= 3
      1770825.04     13944525.00      1770425.00     13944575.00
      1770024.97     13944925.03
#Sta/Elev= 30
  4601.6 2219.16  4644.5 2216.63  4652.0 2215.33  4752.8 2208.01  4773.0 2205.78
  4793.1 2205.01  4823.3 2202.50  4954.4 2194.84  4961.9 2193.62  4967.0 2193.58
  4982.3 2191.06  4982.6 2190.56  4986.5 2190.56  4986.8 2191.06  5011.9 2192.14
  5018.5 2191.83  5032.7 2193.62  5054.6 2194.64  5089.7 2195.17  5111.1 2193.34
  5146.6 2193.29  5238.7 2196.72  5273.8 2197.23  5288.1 2198.17  5422.8 2200.76
  5437.1 2201.29  5465.5 2203.99  5472.2 2203.76  5479.8 2204.58  5536.3 2207.40
#Mann=3,-1,0
  4601.6    0.07       0  4982.3    0.05       0  4986.8    0.07       0
Bank Sta=4982.3,4986.8
Exp/Cntr=0.3,0.1

Type RM Length L Ch R = 1,2832,473,473,473
BEGIN DESCRIPTION:
Stream0116 6.0
END DESCRIPTION:
XS GIS Cut Line= 3
      1770525.04     13944074.98      1770325.00     13944175.00
      1769925.03     13944574.97
#Sta/Elev= 30
  4771.8 2202.16  4794.2 2201.66  4816.6 2199.07  4847.3 2197.11  4852.9 2197.16
  4861.3 2196.49  4869.7 2195.18  4936.8 2191.07  4942.3 2191.42  4950.7 2190.80
  4964.7 2189.52  4990.4 2184.53  4990.7 2184.03  4994.6 2184.03  4995.0 2184.53
  5009.6 2185.58  5037.9 2186.39  5066.2 2188.99  5094.4 2190.16  5122.7 2190.75
  5179.3 2190.90  5306.6 2193.65  5363.1 2195.29  5391.4 2196.58  5405.6 2197.99
  5419.7 2198.03  5448.0 2199.37  5476.3 2199.92  5518.7 2202.55  5561.1 2203.77
#Mann=3,-1,0
  4771.8    0.07       0  4990.4    0.05       0  4995.0    0.07       0
Bank Sta=4990.4,4995
Exp/Cntr=0.3,0.1

Type RM Length L Ch R = 1,2359,443,443,443
BEGIN DESCRIPTION:
Stream0116 5.0
END DESCRIPTION:
XS GIS Cut Line= 3
      1770325.00     13943725.00      1770125.00     13943775.00
      1769724.97     13943674.99
#Sta/Elev= 30
  4798.5 2195.27  4870.7 2193.21  4891.3 2191.85  4945.4 2187.36  4963.4 2183.17
  4981.5 2180.37  4986.6 2180.54  4991.9 2179.83  4992.2 2179.33  4996.5 2179.33
  4996.9 2179.83  5007.2 2179.90  5022.7 2182.23  5027.9 2181.52  5035.6 2182.44
  5056.2 2183.02  5069.1 2182.14  5076.8 2183.56  5097.4 2184.45  5151.5 2185.46
  5159.3 2186.34  5192.8 2186.02  5228.9 2187.00  5234.0 2186.65  5275.2 2188.43
  5303.6 2190.91  5311.3 2192.06  5316.5 2191.73  5393.8 2201.44  5417.0 2203.76
#Mann=3,-1,0
  4798.5    0.07       0  4991.9    0.05       0  4996.9    0.07       0
Bank Sta=4991.9,4996.9
Exp/Cntr=0.3,0.1

Type RM Length L Ch R = 1,1916,447,447,447
BEGIN DESCRIPTION:
Stream0116 4.0
END DESCRIPTION:
XS GIS Cut Line= 3
      1770175.02     13943575.01      1769925.00     13943425.00
      1769824.97     13943425.00
#Sta/Elev= 30
  4707.9 2188.93  4715.7 2189.33  4758.5 2187.46  4774.0 2186.23  4789.6 2185.57
  4801.2 2184.49  4816.8 2184.43  4832.3 2183.11  4838.1 2183.20  4847.9 2182.64
  4875.1 2181.93  4890.6 2180.91  4927.6 2180.09  4933.4 2179.56  4954.8 2179.10
  4976.1 2177.70  4991.7 2177.40  4996.6 2176.00  5002.0 2176.00  5009.5 2175.17
  5017.0 2173.67  5017.3 2173.17  5021.6 2173.17  5022.0 2173.67  5029.5 2179.42
  5039.5 2183.94  5059.5 2187.20  5089.5 2191.61  5097.0 2192.66  5099.5 2192.66
#Mann=3,-1,0
  4707.9    0.07       0  5017.0    0.05       0  5022.0    0.07       0
Bank Sta=5017,5022
Exp/Cntr=0.3,0.1

Type RM Length L Ch R = 1,1469,471,471,471
BEGIN DESCRIPTION:
Stream0116 3.0
END DESCRIPTION:
XS GIS Cut Line= 3
      1770425.01     13943225.01      1770225.00     13943125.00
      1769974.97     13943074.99
#Sta/Elev= 30
  4776.4 2191.96  4779.2 2191.96  4784.8 2191.24  4798.8 2190.74  4851.9 2186.25
  4874.2 2183.48  4896.6 2181.92  4916.2 2180.14  4941.3 2177.04  4946.9 2175.93
  4969.3 2173.94  4997.2 2172.84  5028.1 2172.77  5028.5 2172.27  5032.8 2172.27
  5033.2 2172.77  5040.8 2173.72  5051.0 2174.05  5061.2 2174.99  5071.4 2175.39
  5081.6 2176.68  5091.8 2177.26  5112.2 2179.46  5132.6 2181.22  5163.2 2183.05
  5173.4 2183.95  5183.6 2185.52  5204.0 2186.64  5214.2 2186.89  5255.0 2189.19
#Mann=3,-1,0
  4776.4    0.07       0  5028.1    0.05       0  5033.2    0.07       0
Bank Sta=5028.1,5033.2
Exp/Cntr=0.3,0.1

Type RM Length L Ch R = 1,998,480,480,480
BEGIN DESCRIPTION:
Stream0116 2.0
END DESCRIPTION:
XS GIS Cut Line= 3
      1770525.04     13942725.00      1770425.00     13942725.00
      1770075.03     13942874.99
#Sta/Elev= 30
  4900.4 2185.55  4920.4 2184.42  4940.4 2181.74  4970.4 2178.61  4980.4 2177.91
  4990.4 2174.97  4997.9 2170.94  5003.2 2170.94  5006.9 2165.98  5007.3 2165.48
  5011.7 2165.48  5012.1 2165.98  5033.1 2167.45  5044.0 2168.88  5054.8 2169.18
  5067.5 2170.73  5076.6 2170.68  5098.4 2171.53  5120.1 2173.04  5143.7 2173.98
  5219.9 2175.96  5261.6 2178.13  5272.4 2179.02  5314.1 2181.45  5319.6 2182.23
  5326.8 2182.64  5348.6 2183.70  5359.5 2183.89  5366.7 2184.44  5381.2 2184.75
#Mann=3,-1,0
  4900.4    0.07       0  5006.9    0.05       0  5012.1    0.07       0
Bank Sta=5006.9,5012.1
Exp/Cntr=0.3,0.1

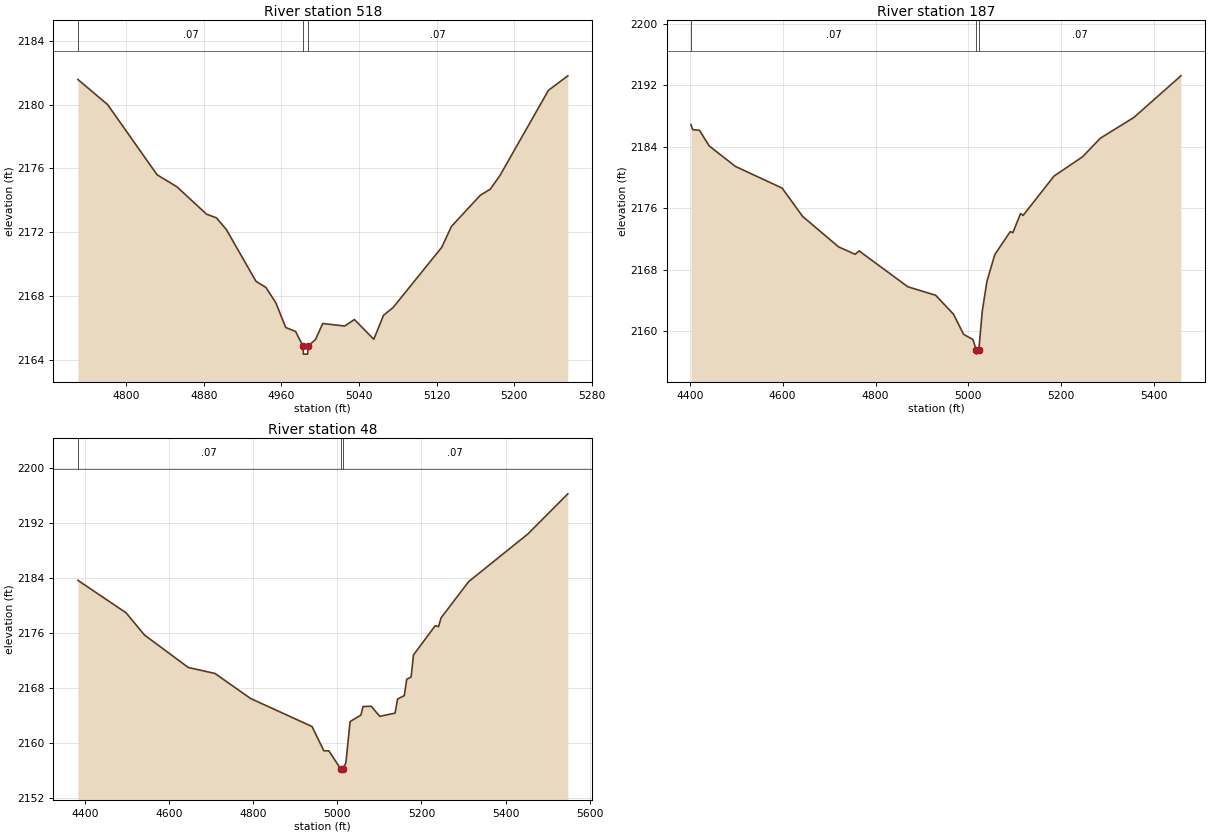
Type RM Length L Ch R = 1,518,331,331,331
BEGIN DESCRIPTION:
Stream0116 1.0
END DESCRIPTION:
XS GIS Cut Line= 3
      1770575.03     13942325.01      1770325.00     13942275.00
      1770074.98     13942275.00
#Sta/Elev= 30
  4750.2 2181.57  4780.8 2180.00  4831.8 2175.60  4852.2 2174.85  4882.8 2173.13
  4893.0 2172.90  4903.2 2172.17  4933.8 2168.92  4944.0 2168.54  4954.2 2167.58
  4964.4 2166.03  4974.6 2165.78  4982.2 2164.86  4982.6 2164.36  4987.0 2164.36
  4987.4 2164.86  4995.0 2165.27  5002.6 2166.28  5025.2 2166.12  5035.2 2166.53
  5055.2 2165.29  5065.2 2166.79  5075.2 2167.29  5125.2 2171.05  5135.2 2172.36
  5165.2 2174.33  5175.2 2174.69  5185.2 2175.55  5235.2 2180.89  5255.2 2181.80
#Mann=3,-1,0
  4750.2    0.07       0  4982.2    0.05       0  4987.4    0.07       0
Bank Sta=4982.2,4987.4
Exp/Cntr=0.3,0.1

Type RM Length L Ch R = 1,187,139,139,139
BEGIN DESCRIPTION:
Stream0116 0.0
END DESCRIPTION:
XS GIS Cut Line= 4
      1770790.41     13942203.84      1770441.46     13941952.25
      1770215.98     13941964.91      1769861.23     13942146.83
#Sta/Elev= 30
  4402.8 2186.88  4406.3 2186.22  4421.0 2186.14  4441.9 2184.11  4498.4 2181.44
  4599.0 2178.62  4643.1 2174.94  4720.5 2170.98  4756.1 2170.01  4764.6 2170.46
  4869.5 2165.79  4929.6 2164.68  4967.9 2162.22  4989.7 2159.60  5009.7 2158.93
  5017.1 2157.53  5017.5 2157.03  5022.4 2157.53  5029.8 2162.59  5039.8 2166.48
  5056.8 2169.97  5090.0 2172.96  5095.6 2172.82  5112.2 2175.30  5117.8 2175.07
  5184.4 2180.19  5245.3 2182.67  5284.1 2185.11  5356.3 2187.81  5457.5 2193.22
#Mann=3,-1,0
  4402.8    0.07       0  5017.1    0.05       0  5022.4    0.07       0
Bank Sta=5017.1,5022.4
Exp/Cntr=0.3,0.1

Type RM Length L Ch R = 1,48,0,0,0
BEGIN DESCRIPTION:
Stream0116 0.1
END DESCRIPTION:
XS GIS Cut Line= 4
      1770863.35     13941980.19      1770373.74     13941811.78
      1770137.63     13941839.56      1769778.26     13942036.51
#Sta/Elev= 30
  4382.8 2183.65  4497.4 2178.92  4541.0 2175.69  4645.4 2170.95  4708.9 2170.08
  4793.5 2166.43  4939.6 2162.35  4967.8 2158.81  4979.8 2158.80  5007.4 2156.20
  5007.8 2155.70  5012.7 2156.20  5020.1 2157.01  5030.2 2163.07  5055.9 2164.01
  5061.0 2165.26  5080.5 2165.30  5100.7 2163.83  5137.1 2164.30  5143.1 2166.35
  5159.2 2166.86  5164.9 2169.24  5175.3 2169.56  5181.0 2172.78  5232.5 2177.03
  5240.7 2176.91  5246.4 2178.17  5312.3 2183.47  5453.1 2190.41  5548.1 2196.26
#Mann=3,-1,0
  4382.8    0.07       0  5007.4    0.05       0  5012.7    0.07       0
Bank Sta=5007.4,5012.7
Exp/Cntr=0.3,0.1

Chan Stop Cuts=-1