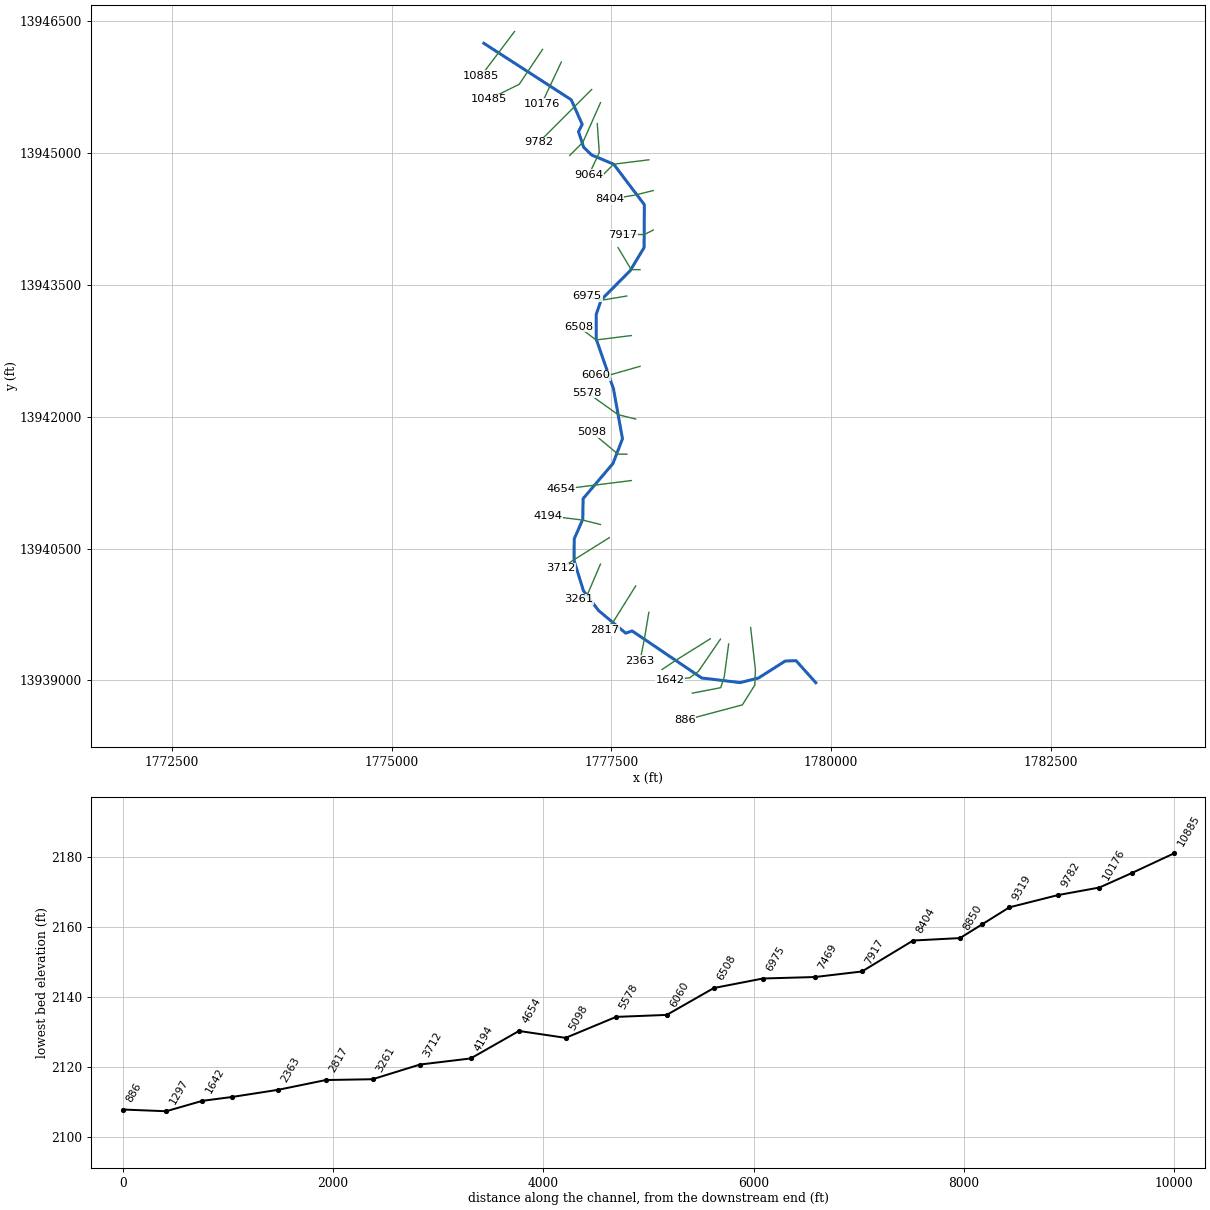
--- Stream0117.prj (project) ---

Proj Title=Stream0117 Base Level Engineering
Current Plan=p01
Default Exp/Contr=0.3,0.1
English Units
Geom File=g01
Flow File=f01
Plan File=p01
BEGIN DESCRIPTION:
Stream0117
END DESCRIPTION:

--- Stream0117.p01 (plan) ---

Plan Title=Multiple Run
Short Identifier=Multiple
Geom File=g01
Flow File=f01
Subcritical Flow
K Sum by GR= 0
Std Step Tol= 0.01
Critical Tol= 0.01
Num of Std Step Trials= 20
Max Error Tol= 0.3
Flow Tol Ratio= 0.001
Split Flow NTrial= 30
Split Flow Tol= 0.02
Split Flow Ratio= 0.02
Log Output Level= 0
Friction Slope Method= 1
Unsteady Friction Slope Method= 2
Unsteady Bridges Friction Slope Method= 1
Parabolic Critical Depth
Global Vel Dist=  1 , 1 , 1
Global Log Level= 0
CheckData=True
Encroach Param= -1, 0, 0, 0
BEGIN DESCRIPTION:
Multiple Run
END DESCRIPTION:

--- Stream0117.f01 (steady flow) ---

Flow Title=Multiple
Number of Profiles=7
Profile Names=10-year,25-year,50-year,1pct_min,100-year,1pct_plu,500-year
River Rch & RM= Stream0117,Reach-1,10885
    1248    2150    3013    2038    4067    8114    7328
River Rch & RM= Stream0117,Reach-1,10176
    1271    2190    3071    2077    4144    8269    7469
River Rch & RM= Stream0117,Reach-1,8850
    1920    3385    4818    3304    6593   13154   12222
River Rch & RM= Stream0117,Reach-1,7917
    2254    3988    5687    3904    7789   15542   14472
Boundary for River Rch & Prof#=Stream0117,Reach-1,1
Up Type=0
Dn Type=3
Dn Slope=0.005
Boundary for River Rch & Prof#=Stream0117,Reach-1,2
Up Type=0
Dn Type=3
Dn Slope=0.005
Boundary for River Rch & Prof#=Stream0117,Reach-1,3
Up Type=0
Dn Type=3
Dn Slope=0.005
Boundary for River Rch & Prof#=Stream0117,Reach-1,4
Up Type=0
Dn Type=3
Dn Slope=0.005
Boundary for River Rch & Prof#=Stream0117,Reach-1,5
Up Type=0
Dn Type=3
Dn Slope=0.005
Boundary for River Rch & Prof#=Stream0117,Reach-1,6
Up Type=0
Dn Type=3
Dn Slope=0.005
Boundary for River Rch & Prof#=Stream0117,Reach-1,7
Up Type=0
Dn Type=3
Dn Slope=0.005

--- Stream0117.g01 (geometry) ---

Geom Title=Existing Conditions

River Reach=Stream0117,Reach-1
Reach XY= 30
      1776048.09     13946250.67      1777042.05     13945608.49
      1777166.90     13945328.29      1777124.79     13945245.21
      1777182.85     13945068.81      1777272.69     13944980.83
      1777525.00     13944875.00      1777873.95     13944414.56
      1777871.25     13943926.55      1777711.37     13943661.79
      1777382.86     13943331.17      1777326.22     13943164.50
      1777326.22     13942885.50      1777522.74     13942319.06
      1777625.20     13941749.92      1777516.84     13941468.95
      1777177.06     13941069.15      1777173.78     13940835.50
      1777075.52     13940609.78      1777074.55     13940364.81
      1777180.52     13940022.57      1777354.58     13939794.77
      1777661.67     13939538.65      1777734.99     13939563.74
      1778526.55     13939028.75      1778964.45     13938976.11
      1779173.53     13939028.55      1779476.56     13939221.26
      1779600.12     13939225.32      1779825.00     13938975.00

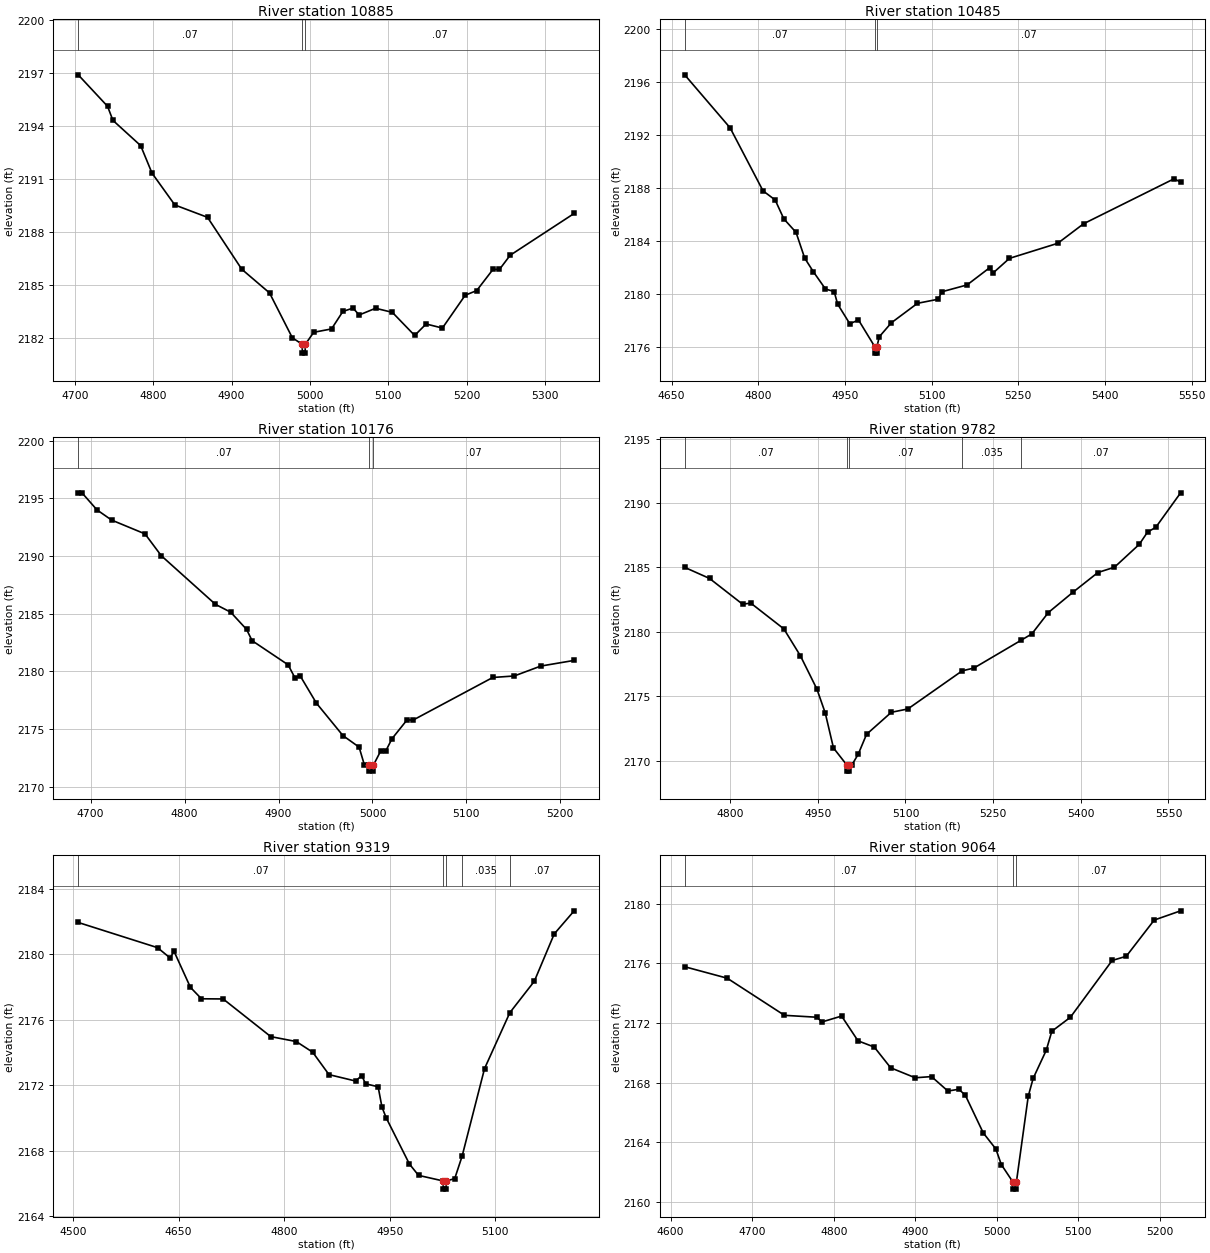
Type RM Length L Ch R = 1,10885,400,400,400
BEGIN DESCRIPTION:
Stream0117 20.0
END DESCRIPTION:
XS GIS Cut Line= 2
      1776397.07     13946384.81      1776015.73     13945879.82
#Sta/Elev= 30
  4704.3 2196.88  4741.7 2195.10  4748.6 2194.30  4784.0 2192.87  4798.5 2191.31
  4827.6 2189.51  4869.3 2188.81  4913.0 2185.87  4948.4 2184.53  4977.5 2181.99
  4990.1 2181.62  4990.3 2181.12  4993.8 2181.12  4994.1 2181.62  5004.8 2182.30
  5027.5 2182.49  5042.0 2183.48  5054.9 2183.67  5062.8 2183.28  5083.7 2183.66
  5105.1 2183.43  5133.6 2182.12  5148.2 2182.77  5169.0 2182.54  5198.1 2184.40
  5212.7 2184.66  5233.5 2185.86  5241.8 2185.86  5255.4 2186.66  5337.1 2189.03
#Mann=3,-1,0
  4704.3    0.07       0  4990.1    0.05       0  4994.1    0.07       0
Bank Sta=4990.1,4994.1
Exp/Cntr=0.3,0.1

Type RM Length L Ch R = 1,10485,309,309,309
BEGIN DESCRIPTION:
Stream0117 19.1
END DESCRIPTION:
XS GIS Cut Line= 3
      1776716.08     13946181.69      1776450.44     13945784.53
      1776109.60     13945615.41
#Sta/Elev= 30
  4672.8 2196.56  4751.4 2192.55  4808.4 2187.78  4829.4 2187.09  4844.4 2185.66
  4865.5 2184.64  4880.5 2182.69  4895.5 2181.66  4916.5 2180.35  4931.5 2180.16
  4937.5 2179.21  4958.6 2177.72  4973.6 2178.01  5001.6 2176.00  5001.8 2175.50
  5005.3 2175.50  5005.6 2176.00  5009.6 2176.74  5030.6 2177.80  5075.7 2179.27
  5111.7 2179.58  5117.7 2180.14  5161.5 2180.66  5200.8 2181.97  5206.4 2181.56
  5234.8 2182.67  5318.4 2183.81  5363.2 2185.29  5520.1 2188.70  5531.1 2188.43
#Mann=3,-1,0
  4672.8    0.07       0  5001.6    0.05       0  5005.6    0.07       0
Bank Sta=5001.6,5005.6
Exp/Cntr=0.3,0.1

Type RM Length L Ch R = 1,10176,394,394,394
BEGIN DESCRIPTION:
Stream0117 19.0
END DESCRIPTION:
XS GIS Cut Line= 2
      1776928.97     13946037.16      1776704.14     13945559.53
#Sta/Elev= 30
  4686.8 2195.47  4690.8 2195.47  4706.8 2193.99  4722.3 2193.11  4757.9 2191.91
  4775.2 2190.02  4832.9 2185.80  4849.1 2185.12  4866.0 2183.63  4871.9 2182.65
  4910.2 2180.56  4917.5 2179.43  4923.0 2179.61  4940.3 2177.24  4968.6 2174.42
  4985.8 2173.42  4991.4 2171.88  4996.4 2171.84  4996.7 2171.34  5000.6 2171.34
  5000.9 2171.84  5008.6 2173.06  5014.2 2173.09  5020.8 2174.15  5037.0 2175.80
  5042.9 2175.75  5128.1 2179.46  5150.9 2179.59  5179.2 2180.45  5214.7 2180.94
#Mann=3,-1,0
  4686.8    0.07       0  4996.4    0.05       0  5000.9    0.07       0
Bank Sta=4996.4,5000.9
Exp/Cntr=0.3,0.1

Type RM Length L Ch R = 1,9782,463,463,463
BEGIN DESCRIPTION:
Stream0117 18.0
END DESCRIPTION:
XS GIS Cut Line= 3
      1777275.03     13945725.03      1777075.00     13945525.00
      1776674.98     13945124.98
#Sta/Elev= 30
  4722.2 2185.01  4764.7 2184.15  4821.2 2182.15  4835.4 2182.23  4891.9 2180.23
  4920.2 2178.14  4948.5 2175.55  4962.7 2173.70  4976.8 2170.98  4999.2 2169.68
  4999.6 2169.18  5003.5 2169.18  5003.8 2169.68  5008.6 2169.68  5019.2 2170.50
  5033.4 2172.04  5075.8 2173.75  5104.1 2174.01  5197.0 2176.97  5217.2 2177.19
  5298.0 2179.35  5316.2 2179.84  5344.5 2181.50  5386.9 2183.09  5429.3 2184.61
  5457.6 2185.02  5500.1 2186.80  5514.2 2187.75  5528.3 2188.12  5570.8 2190.80
#Mann=5,-1,0
  4722.2    0.07       0  4999.2    0.05       0  5003.8    0.07       0
  5197.0   0.035       0  5298.0    0.07       0
Bank Sta=4999.2,5003.8
Exp/Cntr=0.3,0.1

Type RM Length L Ch R = 1,9319,255,255,255
BEGIN DESCRIPTION:
Stream0117 17.0
END DESCRIPTION:
XS GIS Cut Line= 3
      1777375.00     13945575.00      1777175.00     13945125.00
      1777024.98     13944974.98
#Sta/Elev= 30
  4507.5 2181.94  4620.3 2180.40  4638.1 2179.77  4643.6 2180.18  4666.9 2177.98
  4682.6 2177.28  4713.4 2177.27  4781.1 2174.97  4817.3 2174.67  4840.6 2174.02
  4863.8 2172.65  4901.5 2172.26  4910.3 2172.59  4915.8 2172.09  4933.6 2171.91
  4939.1 2170.66  4945.2 2170.00  4978.1 2167.19  4991.0 2166.50  5025.9 2166.16
  5026.2 2165.66  5030.2 2165.66  5030.5 2166.16  5042.4 2166.30  5052.9 2167.67
  5084.8 2173.02  5120.7 2176.43  5155.5 2178.35  5183.8 2181.24  5212.1 2182.65
#Mann=5,-1,0
  4507.5    0.07       0  5025.9    0.05       0  5030.5    0.07       0
  5052.9   0.035       0  5120.7    0.07       0
Bank Sta=5025.9,5030.5
Exp/Cntr=0.3,0.1

Type RM Length L Ch R = 1,9064,214,214,214
BEGIN DESCRIPTION:
Stream0117 16.1
END DESCRIPTION:
XS GIS Cut Line= 3
      1777338.03     13945337.06      1777361.46     13945007.74
      1777243.60     13944755.69
#Sta/Elev= 30
  4617.2 2175.78  4669.4 2175.01  4739.6 2172.52  4779.7 2172.39  4785.3 2172.07
  4809.7 2172.47  4829.8 2170.81  4849.8 2170.39  4869.9 2169.00  4900.0 2168.33
  4920.0 2168.41  4940.1 2167.44  4953.4 2167.56  4961.4 2167.17  4983.5 2164.63
  4999.0 2163.55  5005.6 2162.51  5019.6 2161.36  5019.9 2160.86  5023.9 2160.86
  5024.2 2161.36  5038.7 2167.10  5044.7 2168.29  5060.8 2170.18  5067.6 2171.45
  5090.4 2172.39  5141.6 2176.20  5158.9 2176.48  5193.2 2178.91  5225.6 2179.53
#Mann=3,-1,0
  4617.2    0.07       0  5019.6    0.05       0  5024.2    0.07       0
Bank Sta=5019.6,5024.2
Exp/Cntr=0.3,0.1

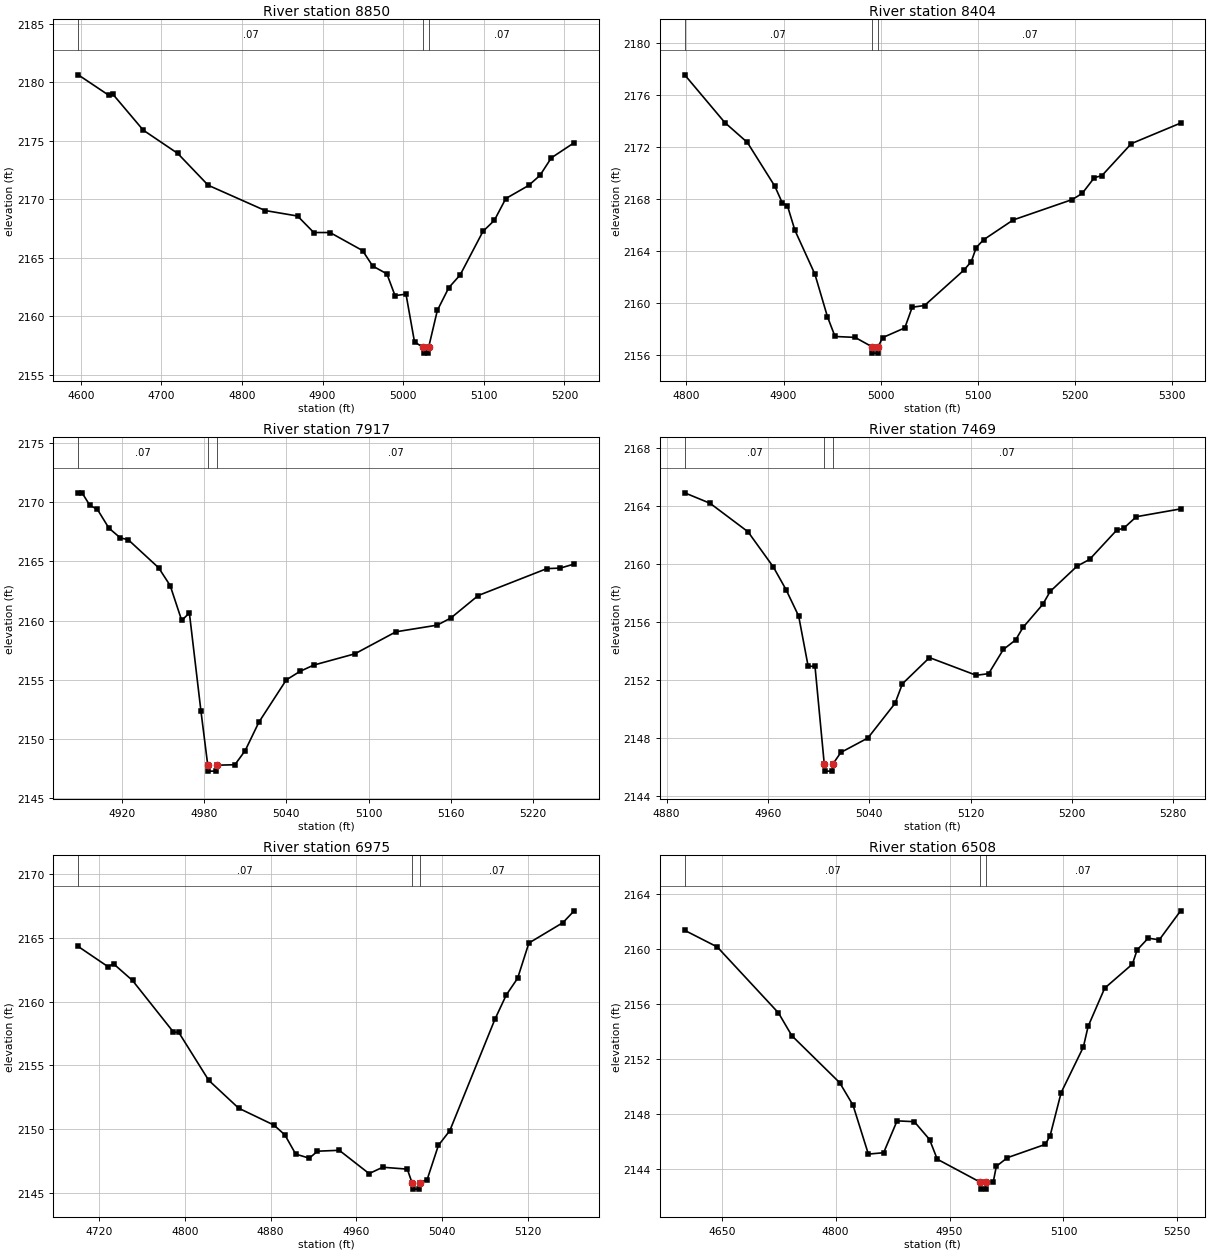
Type RM Length L Ch R = 1,8850,446,446,446
BEGIN DESCRIPTION:
Stream0117 16.0
END DESCRIPTION:
XS GIS Cut Line= 3
      1777924.99     13944925.00      1777525.00     13944875.00
      1777375.02     13944725.02
#Sta/Elev= 30
  4596.9 2180.63  4634.7 2178.89  4639.7 2178.99  4677.5 2175.91  4720.3 2173.92
  4758.1 2171.20  4828.7 2169.04  4869.0 2168.57  4889.1 2167.16  4909.3 2167.16
  4949.6 2165.62  4962.2 2164.30  4979.8 2163.63  4989.9 2161.77  5003.5 2161.90
  5014.1 2157.80  5025.0 2157.36  5025.5 2156.86  5031.1 2156.86  5031.6 2157.36
  5042.4 2160.51  5056.6 2162.45  5070.7 2163.54  5099.0 2167.26  5113.1 2168.20
  5127.3 2170.06  5155.6 2171.18  5169.7 2172.04  5183.8 2173.54  5212.1 2174.83
#Mann=3,-1,0
  4596.9    0.07       0  5025.0    0.05       0  5031.6    0.07       0
Bank Sta=5025,5031.6
Exp/Cntr=0.3,0.1

Type RM Length L Ch R = 1,8404,487,487,487
BEGIN DESCRIPTION:
Stream0117 15.0
END DESCRIPTION:
XS GIS Cut Line= 3
      1777975.04     13944575.01      1777775.00     13944525.00
      1777475.04     13944475.01
#Sta/Elev= 30
  4798.2 2177.56  4839.5 2173.89  4862.7 2172.36  4891.0 2168.99  4898.7 2167.70
  4903.9 2167.50  4911.6 2165.61  4932.2 2162.23  4945.1 2158.96  4952.9 2157.44
  4973.5 2157.37  4990.7 2156.66  4991.2 2156.16  4996.9 2156.16  4997.4 2156.66
  5001.8 2157.35  5024.7 2158.10  5032.3 2159.69  5045.0 2159.82  5085.5 2162.54
  5093.1 2163.20  5098.2 2164.28  5105.8 2164.88  5136.2 2166.40  5197.0 2167.97
  5207.2 2168.44  5219.8 2169.66  5227.4 2169.80  5257.8 2172.27  5308.5 2173.85
#Mann=3,-1,0
  4798.2    0.07       0  4990.7    0.05       0  4997.4    0.07       0
Bank Sta=4990.7,4997.4
Exp/Cntr=0.3,0.1

Type RM Length L Ch R = 1,7917,448,448,448
BEGIN DESCRIPTION:
Stream0117 14.0
END DESCRIPTION:
XS GIS Cut Line= 3
      1777975.03     13944125.02      1777875.00     13944075.00
      1777625.04     13944075.00
#Sta/Elev= 30
  4888.2 2170.78  4891.0 2170.78  4896.6 2169.74  4902.2 2169.38  4910.6 2167.80
  4919.0 2166.97  4924.6 2166.83  4946.9 2164.45  4955.3 2162.95  4963.7 2160.01
  4969.3 2160.64  4977.7 2152.39  4982.7 2147.79  4983.2 2147.29  4988.9 2147.29
  4989.4 2147.79  5002.5 2147.83  5010.0 2149.02  5020.0 2151.42  5040.0 2154.99
  5050.0 2155.71  5060.0 2156.24  5090.0 2157.19  5120.0 2159.05  5150.0 2159.61
  5160.0 2160.21  5180.0 2162.11  5230.0 2164.38  5240.0 2164.43  5250.0 2164.77
#Mann=3,-1,0
  4888.2    0.07       0  4982.7    0.05       0  4989.4    0.07       0
Bank Sta=4982.7,4989.4
Exp/Cntr=0.3,0.1

Type RM Length L Ch R = 1,7469,494,494,494
BEGIN DESCRIPTION:
Stream0117 13.0
END DESCRIPTION:
XS GIS Cut Line= 3
      1777825.02     13943675.00      1777725.00     13943675.00
      1777574.99     13943925.02
#Sta/Elev= 30
  4894.3 2164.92  4914.3 2164.20  4944.3 2162.23  4964.3 2159.80  4974.3 2158.24
  4984.3 2156.41  4991.8 2152.94  4997.2 2152.94  5004.5 2146.20  5005.0 2145.70
  5010.9 2145.70  5011.4 2146.20  5017.6 2146.99  5039.0 2147.99  5060.4 2150.38
  5066.2 2151.73  5087.6 2153.54  5124.5 2152.32  5134.3 2152.43  5145.9 2154.10
  5155.6 2154.76  5161.5 2155.63  5177.0 2157.21  5182.9 2158.11  5204.2 2159.86
  5214.0 2160.32  5235.3 2162.33  5241.2 2162.49  5250.9 2163.27  5285.9 2163.81
#Mann=3,-1,0
  4894.3    0.07       0  5004.5    0.05       0  5011.4    0.07       0
Bank Sta=5004.5,5011.4
Exp/Cntr=0.3,0.1

Type RM Length L Ch R = 1,6975,467,467,467
BEGIN DESCRIPTION:
Stream0117 12.0
END DESCRIPTION:
XS GIS Cut Line= 3
      1777674.95     13943374.99      1777375.00     13943325.00
      1777225.00     13943375.00
#Sta/Elev= 30
  4700.7 2164.34  4728.5 2162.75  4733.6 2162.98  4751.3 2161.67  4789.4 2157.62
  4794.4 2157.59  4822.3 2153.83  4850.2 2151.64  4883.1 2150.31  4893.3 2149.54
  4903.4 2148.03  4916.1 2147.71  4923.7 2148.26  4944.0 2148.33  4971.8 2146.50
  4984.5 2147.00  5007.4 2146.85  5011.8 2145.78  5012.3 2145.28  5018.3 2145.28
  5018.8 2145.78  5025.9 2146.03  5036.4 2148.72  5047.0 2149.87  5089.1 2158.63
  5099.7 2160.54  5110.2 2161.84  5120.7 2164.61  5152.4 2166.21  5162.9 2167.14
#Mann=3,-1,0
  4700.7    0.07       0  5011.8    0.05       0  5018.8    0.07       0
Bank Sta=5011.8,5018.8
Exp/Cntr=0.3,0.1

Type RM Length L Ch R = 1,6508,448,448,448
BEGIN DESCRIPTION:
Stream0117 11.0
END DESCRIPTION:
XS GIS Cut Line= 3
      1777725.02     13942925.00      1777325.00     13942875.00
      1777125.03     13943024.98
#Sta/Elev= 30
  4601.2 2161.39  4644.1 2160.18  4724.7 2155.38  4742.3 2153.72  4805.3 2150.30
  4822.9 2148.66  4843.1 2145.10  4863.2 2145.20  4880.9 2147.52  4903.6 2147.46
  4923.7 2146.16  4933.8 2144.73  4990.6 2143.05  4991.1 2142.55  4997.4 2142.55
  4997.9 2143.05  5007.5 2143.05  5011.6 2144.21  5026.2 2144.84  5076.2 2145.81
  5082.5 2146.45  5097.0 2149.58  5126.2 2152.89  5132.5 2154.40  5154.3 2157.18
  5190.8 2158.93  5197.0 2159.96  5211.6 2160.82  5226.2 2160.70  5254.3 2162.81
#Mann=3,-1,0
  4601.2    0.07       0  4990.6    0.05       0  4997.9    0.07       0
Bank Sta=4990.6,4997.9
Exp/Cntr=0.3,0.1

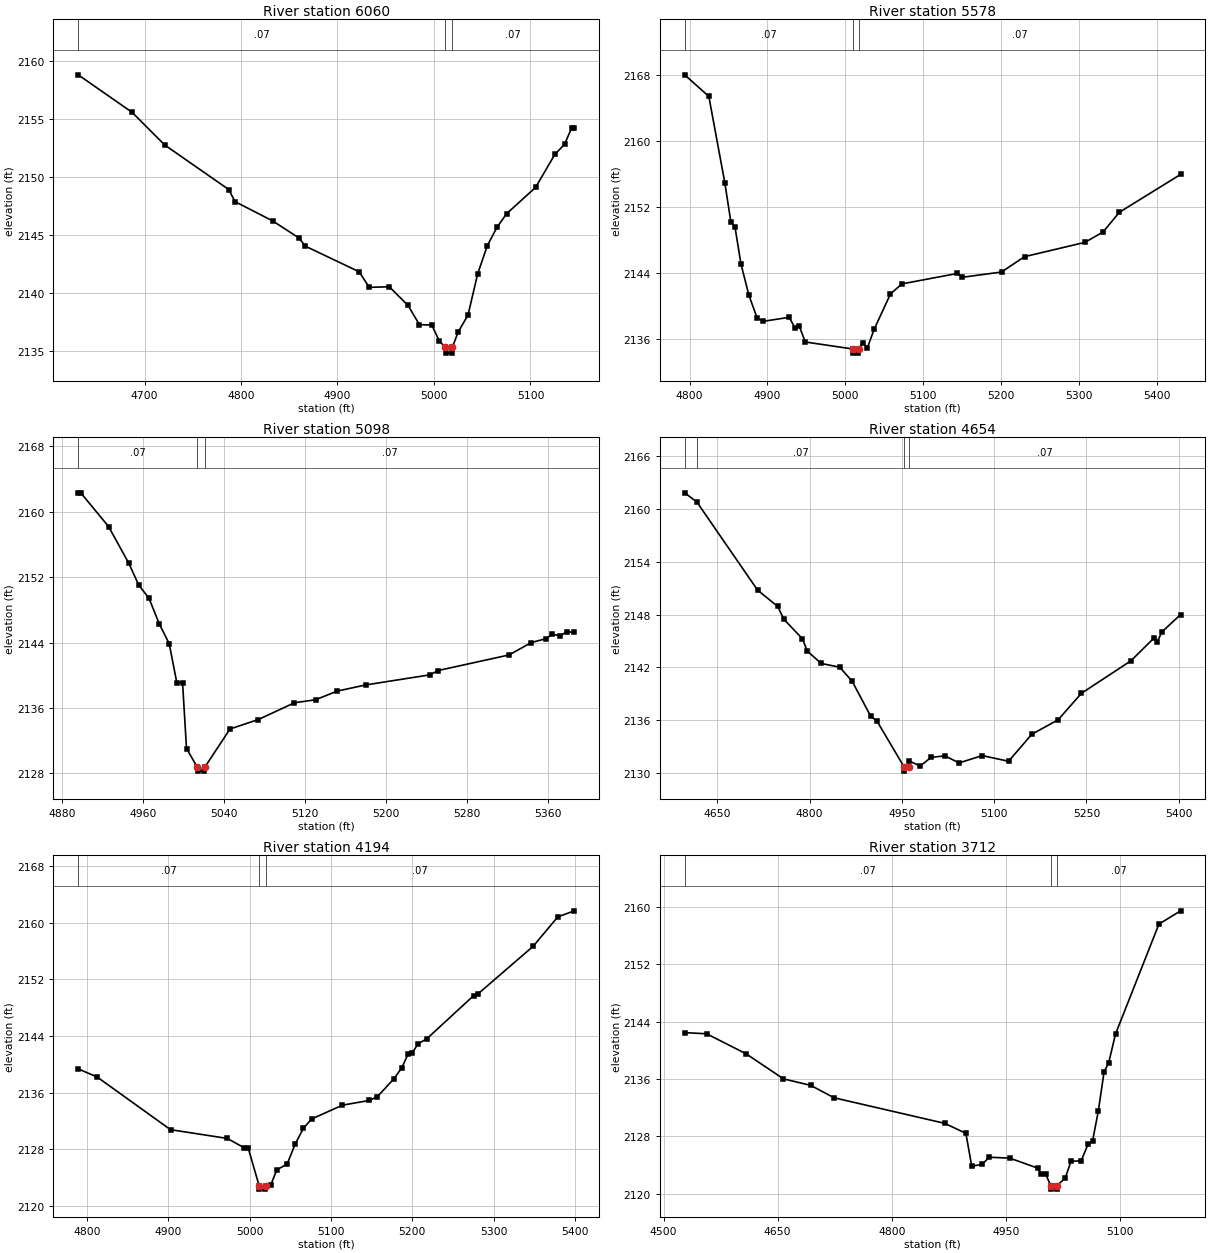
Type RM Length L Ch R = 1,6060,482,482,482
BEGIN DESCRIPTION:
Stream0117 10.0
END DESCRIPTION:
XS GIS Cut Line= 3
      1777825.04     13942575.01      1777475.00     13942475.00
      1777325.05     13942475.00
#Sta/Elev= 30
  4631.3 2158.80  4687.2 2155.57  4721.0 2152.76  4787.3 2148.93  4793.8 2147.89
  4832.8 2146.23  4860.1 2144.76  4866.6 2144.06  4922.5 2141.85  4932.9 2140.51
  4953.7 2140.56  4973.2 2138.95  4984.9 2137.30  4997.8 2137.27  5005.3 2135.93
  5011.6 2135.35  5012.1 2134.85  5018.5 2134.85  5019.0 2135.35  5025.3 2136.70
  5035.3 2138.13  5045.3 2141.67  5055.3 2144.10  5065.3 2145.67  5075.3 2146.85
  5105.3 2149.11  5125.3 2151.95  5135.3 2152.82  5142.8 2154.24  5145.3 2154.24
#Mann=3,-1,0
  4631.3    0.07       0  5011.6    0.05       0  5019.0    0.07       0
Bank Sta=5011.6,5019
Exp/Cntr=0.3,0.1

Type RM Length L Ch R = 1,5578,480,480,480
BEGIN DESCRIPTION:
Stream0117 9.0
END DESCRIPTION:
XS GIS Cut Line= 3
      1777775.04     13941974.99      1777575.00     13942025.00
      1777225.01     13942274.99
#Sta/Elev= 30
  4793.8 2168.01  4824.8 2165.39  4845.4 2154.87  4853.1 2150.14  4858.3 2149.60
  4866.0 2145.08  4876.3 2141.27  4886.6 2138.58  4894.3 2138.13  4927.8 2138.62
  4935.6 2137.30  4940.7 2137.58  4948.5 2135.63  5009.7 2134.78  5010.2 2134.28
  5016.8 2134.28  5017.3 2134.78  5022.1 2135.51  5028.3 2134.95  5036.9 2137.17
  5057.8 2141.45  5072.5 2142.67  5143.8 2143.94  5149.9 2143.47  5200.3 2144.11
  5229.8 2145.97  5307.2 2147.70  5330.6 2148.96  5351.5 2151.35  5430.1 2155.94
#Mann=3,-1,0
  4793.8    0.07       0  5009.7    0.05       0  5017.3    0.07       0
Bank Sta=5009.7,5017.3
Exp/Cntr=0.3,0.1

Type RM Length L Ch R = 1,5098,444,444,444
BEGIN DESCRIPTION:
Stream0117 8.0
END DESCRIPTION:
XS GIS Cut Line= 3
      1777674.98     13941575.00      1777575.00     13941575.00
      1777274.99     13941825.01
#Sta/Elev= 30
  4895.6 2162.31  4898.1 2162.31  4925.6 2158.19  4945.6 2153.70  4955.6 2151.00
  4965.6 2149.42  4975.6 2146.32  4985.6 2143.86  4993.1 2139.10  4998.8 2139.10
  5002.7 2131.03  5013.3 2128.77  5013.8 2128.27  5020.4 2128.27  5020.9 2128.77
  5045.7 2133.42  5073.7 2134.58  5109.5 2136.63  5130.3 2137.00  5151.8 2138.06
  5179.8 2138.81  5243.6 2140.05  5251.4 2140.57  5321.7 2142.48  5343.8 2144.00
  5358.1 2144.46  5364.6 2145.00  5372.4 2144.83  5378.9 2145.33  5386.1 2145.23
#Mann=3,-1,0
  4895.6    0.07       0  5013.3    0.05       0  5020.9    0.07       0
Bank Sta=5013.3,5020.9
Exp/Cntr=0.3,0.1

Type RM Length L Ch R = 1,4654,460,460,460
BEGIN DESCRIPTION:
Stream0117 7.0
END DESCRIPTION:
XS GIS Cut Line= 3
      1777725.04     13941275.00      1777325.00     13941225.00
      1776924.96     13941175.00
#Sta/Elev= 30
  4596.9 2161.80  4616.8 2160.75  4715.4 2150.77  4748.1 2148.92  4758.2 2147.46
  4788.4 2145.25  4796.0 2143.88  4818.7 2142.46  4848.9 2142.03  4869.0 2140.46
  4899.3 2136.48  4909.4 2135.94  4953.4 2130.75  4953.9 2130.25  4961.1 2130.75
  4962.3 2131.38  4979.9 2130.83  4997.5 2131.81  5020.2 2131.98  5042.9 2131.18
  5080.7 2132.01  5123.5 2131.37  5161.3 2134.43  5204.1 2136.07  5241.9 2139.07
  5322.5 2142.76  5360.3 2145.37  5365.4 2144.94  5372.9 2146.04  5403.2 2148.00
#Mann=4,-1,0
  4596.9   0.035       0  4616.8    0.07       0  4953.4    0.05       0
  4961.1    0.07       0
Bank Sta=4953.4,4961.1
Exp/Cntr=0.3,0.1

Type RM Length L Ch R = 1,4194,482,482,482
BEGIN DESCRIPTION:
Stream0117 6.0
END DESCRIPTION:
XS GIS Cut Line= 3
      1777375.01     13940775.00      1777175.00     13940825.00
      1776774.98     13940875.00
#Sta/Elev= 30
  4789.5 2139.34  4812.7 2138.20  4902.9 2130.76  4972.5 2129.53  4993.1 2128.23
  4998.2 2128.23  5011.7 2122.87  5012.2 2122.37  5019.4 2122.37  5019.9 2122.87
  5025.9 2122.91  5033.5 2125.10  5046.1 2125.89  5056.1 2128.73  5066.2 2130.97
  5076.3 2132.27  5114.1 2134.22  5146.8 2134.88  5156.9 2135.40  5177.1 2137.91
  5187.1 2139.50  5194.7 2141.44  5199.7 2141.57  5207.3 2142.92  5217.4 2143.55
  5275.3 2149.68  5280.4 2149.90  5348.4 2156.64  5378.6 2160.78  5398.8 2161.65
#Mann=3,-1,0
  4789.5    0.07       0  5011.7    0.05       0  5019.9    0.07       0
Bank Sta=5011.7,5019.9
Exp/Cntr=0.3,0.1

Type RM Length L Ch R = 1,3712,451,451,451
BEGIN DESCRIPTION:
Stream0117 5.0
END DESCRIPTION:
XS GIS Cut Line= 3
      1777475.03     13940625.02      1777075.00     13940375.00
      1776925.01     13940275.01
#Sta/Elev= 30
  4527.8 2142.46  4556.7 2142.29  4608.6 2139.50  4657.6 2136.01  4693.5 2135.10
  4724.2 2133.37  4869.8 2129.80  4897.5 2128.41  4905.2 2123.83  4918.8 2124.08
  4928.2 2125.08  4955.3 2124.95  4991.9 2123.56  4996.6 2122.72  5002.5 2122.72
  5008.9 2121.13  5009.4 2120.63  5016.7 2120.63  5017.2 2121.13  5028.1 2122.16
  5035.6 2124.51  5049.1 2124.58  5058.1 2126.89  5064.1 2127.37  5071.6 2131.52
  5079.2 2137.01  5085.2 2138.22  5094.2 2142.26  5151.3 2157.59  5179.8 2159.44
#Mann=3,-1,0
  4527.8    0.07       0  5008.9    0.05       0  5017.2    0.07       0
Bank Sta=5008.9,5017.2
Exp/Cntr=0.3,0.1

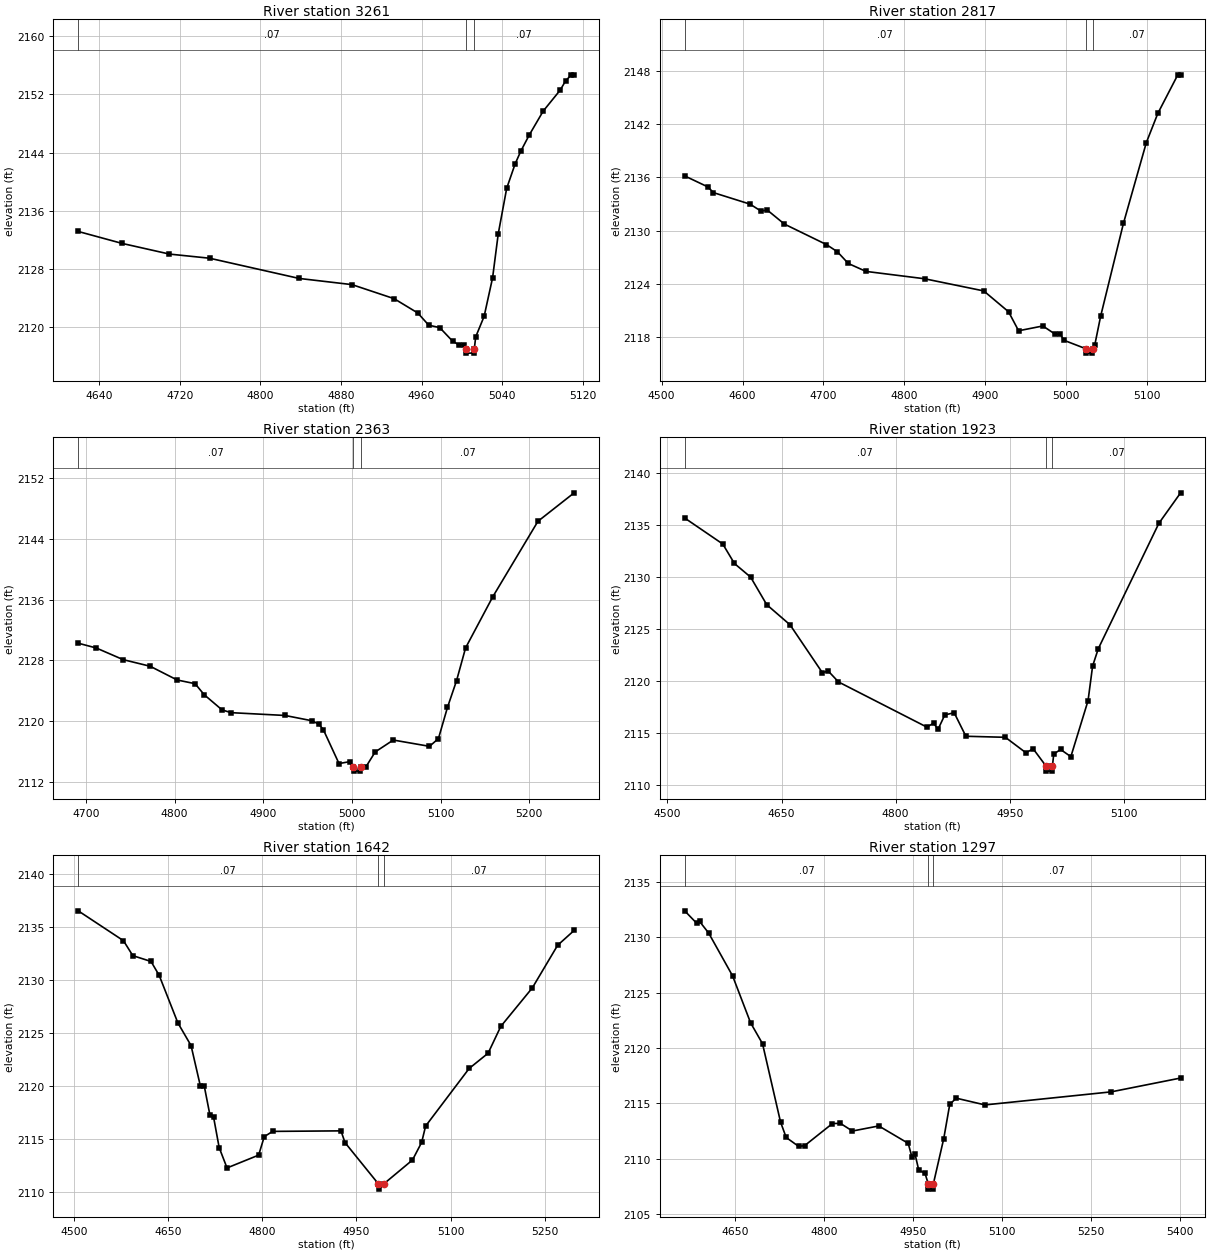
Type RM Length L Ch R = 1,3261,444,444,444
BEGIN DESCRIPTION:
Stream0117 4.0
END DESCRIPTION:
XS GIS Cut Line= 3
      1777374.98     13940324.96      1777225.00     13939975.00
      1777125.04     13939925.02
#Sta/Elev= 30
  4619.0 2133.15  4662.5 2131.51  4709.6 2130.04  4749.5 2129.47  4838.4 2126.69
  4890.9 2125.84  4932.7 2123.91  4956.2 2121.94  4967.1 2120.26  4978.0 2119.93
  4990.7 2118.08  4997.0 2117.56  5002.5 2117.56  5004.0 2116.92  5004.5 2116.42
  5011.8 2116.42  5012.3 2116.92  5013.7 2118.64  5022.1 2121.48  5030.5 2126.78
  5036.1 2132.81  5044.5 2139.08  5052.9 2142.45  5058.4 2144.16  5066.8 2146.39
  5080.8 2149.71  5097.6 2152.58  5103.2 2153.90  5108.8 2154.69  5111.5 2154.69
#Mann=3,-1,0
  4619.0    0.07       0  5004.0    0.05       0  5012.3    0.07       0
Bank Sta=5004,5012.3
Exp/Cntr=0.3,0.1

Type RM Length L Ch R = 1,2817,454,454,454
BEGIN DESCRIPTION:
Stream0117 3.0
END DESCRIPTION:
XS GIS Cut Line= 3
      1777775.02     13940075.02      1777525.00     13939675.00
      1777425.04     13939575.04
#Sta/Elev= 30
  4528.5 2136.16  4557.4 2134.91  4563.9 2134.28  4609.3 2132.98  4622.9 2132.19
  4630.5 2132.32  4651.8 2130.73  4703.6 2128.43  4717.2 2127.62  4730.8 2126.29
  4752.6 2125.40  4825.1 2124.57  4898.2 2123.20  4928.9 2120.85  4941.3 2118.71
  4971.3 2119.25  4986.7 2118.31  4992.6 2118.37  4997.3 2117.64  5024.3 2116.69
  5024.8 2116.19  5032.2 2116.19  5032.7 2116.69  5035.6 2117.16  5042.7 2120.34
  5070.9 2130.81  5099.2 2139.91  5113.4 2143.20  5138.1 2147.55  5141.6 2147.55
#Mann=3,-1,0
  4528.5    0.07       0  5024.3    0.05       0  5032.7    0.07       0
Bank Sta=5024.3,5032.7
Exp/Cntr=0.3,0.1

Type RM Length L Ch R = 1,2363,440,440,440
BEGIN DESCRIPTION:
Stream0117 2.0
END DESCRIPTION:
XS GIS Cut Line= 3
      1777925.00     13939775.03      1777875.00     13939475.00
      1777825.00     13939225.02
#Sta/Elev= 30
  4691.4 2130.26  4711.7 2129.63  4742.1 2128.09  4772.5 2127.22  4802.9 2125.41
  4823.2 2124.92  4833.4 2123.47  4853.6 2121.46  4863.8 2121.10  4924.6 2120.73
  4955.0 2120.03  4962.6 2119.58  4967.7 2118.87  4985.4 2114.39  4998.1 2114.65
  5001.5 2113.89  5002.0 2113.39  5009.5 2113.39  5010.0 2113.89  5016.0 2114.00
  5026.2 2115.92  5046.6 2117.49  5087.4 2116.66  5097.5 2117.68  5107.7 2121.80
  5117.9 2125.31  5128.1 2129.64  5158.7 2136.37  5209.7 2146.34  5250.5 2150.09
#Mann=3,-1,0
  4691.4    0.07       0  5001.5    0.05       0  5010.0    0.07       0
Bank Sta=5001.5,5010
Exp/Cntr=0.3,0.1

Type RM Length L Ch R = 1,1923,281,281,281
BEGIN DESCRIPTION:
Stream0117 1.0
END DESCRIPTION:
XS GIS Cut Line= 3
      1778624.98     13939474.99      1778225.00     13939225.00
      1778074.97     13939124.98
#Sta/Elev= 30
  4522.6 2135.65  4572.7 2133.15  4588.0 2131.28  4609.3 2129.97  4630.5 2127.32
  4661.1 2125.39  4703.6 2120.79  4711.3 2120.95  4724.8 2119.90  4841.0 2115.56
  4849.8 2115.94  4855.7 2115.35  4864.6 2116.73  4876.9 2116.94  4892.3 2114.68
  4944.2 2114.58  4971.3 2113.09  4980.7 2113.48  4997.5 2111.83  4998.0 2111.33
  5005.6 2111.33  5006.1 2111.83  5007.8 2112.97  5016.8 2113.41  5030.3 2112.72
  5052.9 2118.10  5058.9 2121.43  5066.4 2123.10  5146.0 2135.14  5174.6 2138.07
#Mann=3,-1,0
  4522.6    0.07       0  4997.5    0.05       0  5006.1    0.07       0
Bank Sta=4997.5,5006.1
Exp/Cntr=0.3,0.1

Type RM Length L Ch R = 1,1642,345,345,345
BEGIN DESCRIPTION:
Stream0117 0.1
END DESCRIPTION:
XS GIS Cut Line= 4
      1778739.81     13939470.81      1778490.35     13939105.36
      1778391.04     13939031.14      1778168.94     13939004.06
#Sta/Elev= 30
  4506.7 2136.50  4578.8 2133.68  4593.7 2132.27  4622.7 2131.72  4635.7 2130.41
  4665.5 2125.92  4686.5 2123.78  4701.4 2119.95  4707.5 2119.97  4716.4 2117.27
  4722.4 2117.02  4731.3 2114.15  4743.8 2112.23  4794.2 2113.44  4803.1 2115.18
  4816.4 2115.68  4925.4 2115.73  4931.8 2114.62  4984.9 2110.73  4985.4 2110.23
  4993.7 2110.73  5039.3 2112.98  5053.9 2114.64  5060.2 2116.18  5129.6 2121.62
  5159.8 2123.06  5180.0 2125.59  5230.3 2129.23  5270.6 2133.25  5296.9 2134.65
#Mann=3,-1,0
  4506.7    0.07       0  4984.9    0.05       0  4993.7    0.07       0
Bank Sta=4984.9,4993.7
Exp/Cntr=0.3,0.1

Type RM Length L Ch R = 1,1297,411,411,411
BEGIN DESCRIPTION:
Stream0117 0.0
END DESCRIPTION:
XS GIS Cut Line= 4
      1778833.32     13939414.97      1778783.29     13939041.91
      1778742.77     13938918.14      1778420.18     13938855.74
#Sta/Elev= 30
  4565.4 2132.40  4585.4 2131.29  4590.5 2131.44  4605.7 2130.40  4646.1 2126.52
  4676.4 2122.28  4696.5 2120.39  4726.8 2113.32  4736.3 2111.92  4757.1 2111.12
  4767.2 2111.17  4814.3 2113.18  4827.7 2113.19  4847.9 2112.50  4892.3 2112.96
  4941.8 2111.39  4948.1 2110.16  4953.4 2110.39  4959.6 2108.97  4970.1 2108.68
  4975.5 2107.75  4976.0 2107.25  4983.8 2107.25  4984.3 2107.75  5001.7 2111.82
  5011.8 2114.91  5022.7 2115.47  5071.1 2114.86  5283.7 2116.04  5400.6 2117.29
#Mann=3,-1,0
  4565.4    0.07       0  4975.5    0.05       0  4984.3    0.07       0
Bank Sta=4975.5,4984.3
Exp/Cntr=0.3,0.1

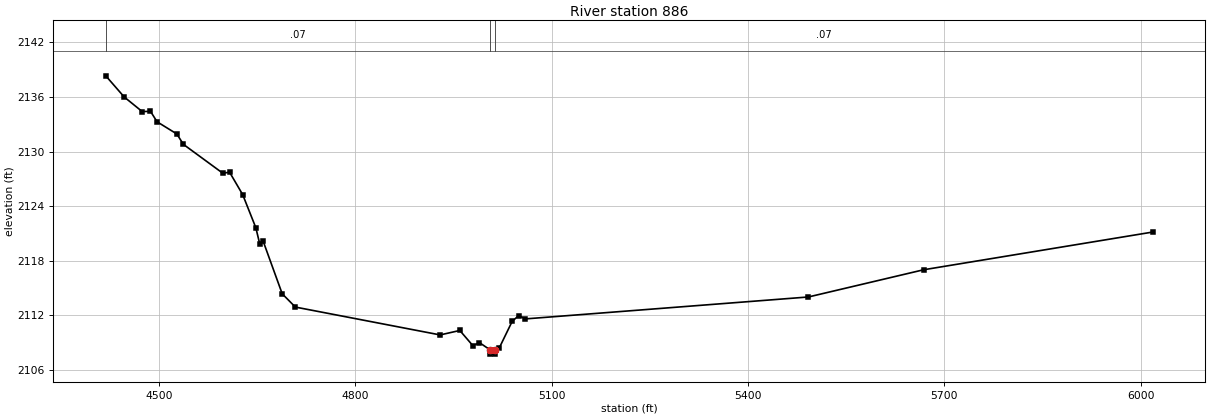
Type RM Length L Ch R = 1,886,0,0,0
BEGIN DESCRIPTION:
Stream0117 0.2
END DESCRIPTION:
XS GIS Cut Line= 5
      1779083.47     13939602.89      1779138.15     13939118.56
      1779130.34     13938946.69      1778989.71     13938722.73
      1778336.10     13938548.26
#Sta/Elev= 30
  4418.5 2138.32  4446.6 2136.00  4474.2 2134.39  4486.8 2134.42  4496.9 2133.27
  4527.1 2131.93  4537.1 2130.79  4597.5 2127.61  4607.6 2127.74  4627.7 2125.27
  4647.8 2121.63  4653.9 2119.81  4659.0 2120.15  4688.1 2114.37  4708.2 2112.91
  4929.5 2109.85  4959.5 2110.34  4979.5 2108.67  4989.6 2109.00  5005.2 2108.24
  5005.7 2107.74  5013.5 2107.74  5014.0 2108.24  5019.6 2108.39  5039.6 2111.35
  5049.6 2111.98  5059.6 2111.61  5492.2 2114.02  5668.3 2117.01  6018.9 2121.16
#Mann=3,-1,0
  4418.5    0.07       0  5005.2    0.05       0  5014.0    0.07       0
Bank Sta=5005.2,5014
Exp/Cntr=0.3,0.1

Chan Stop Cuts=-1