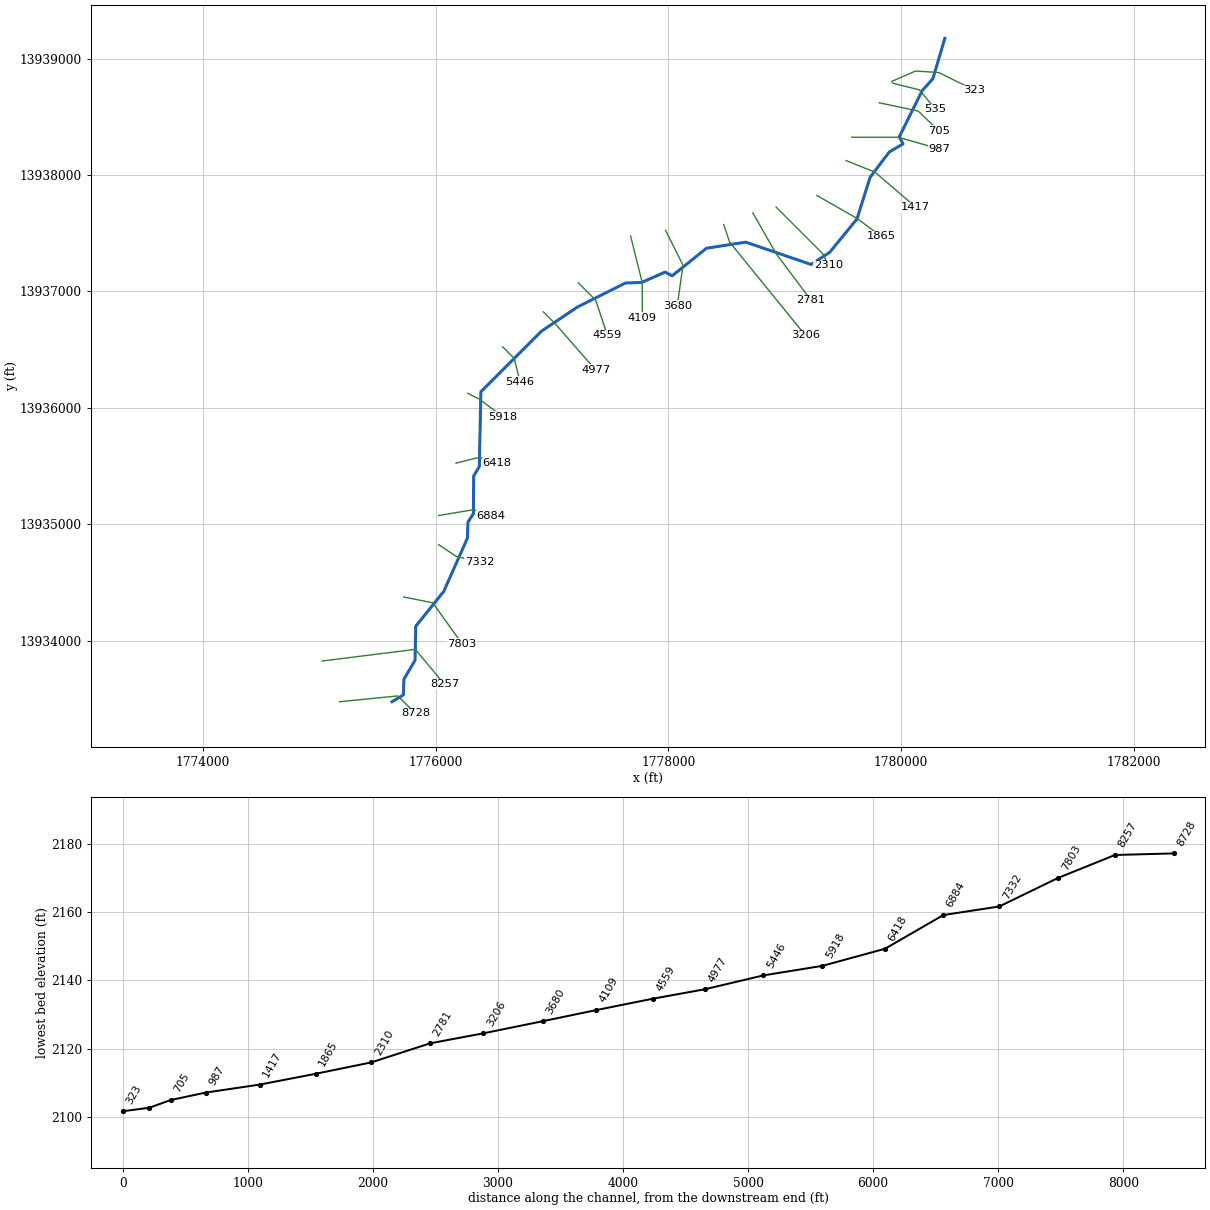
--- Stream0118.prj (project) ---

Proj Title=Stream0118 Base Level Engineering
Current Plan=p01
Default Exp/Contr=0.3,0.1
English Units
Geom File=g01
Flow File=f01
Plan File=p01
BEGIN DESCRIPTION:
Stream0118
END DESCRIPTION:

--- Stream0118.p01 (plan) ---

Plan Title=Multiple Run
Short Identifier=Multiple
Geom File=g01
Flow File=f01
Subcritical Flow
K Sum by GR= 0
Std Step Tol= 0.01
Critical Tol= 0.01
Num of Std Step Trials= 20
Max Error Tol= 0.3
Flow Tol Ratio= 0.001
Split Flow NTrial= 30
Split Flow Tol= 0.02
Split Flow Ratio= 0.02
Log Output Level= 0
Friction Slope Method= 1
Unsteady Friction Slope Method= 2
Unsteady Bridges Friction Slope Method= 1
Parabolic Critical Depth
Global Vel Dist=  1 , 1 , 1
Global Log Level= 0
CheckData=True
Encroach Param= -1, 0, 0, 0
BEGIN DESCRIPTION:
Multiple Run
END DESCRIPTION:

--- Stream0118.f01 (steady flow) ---

Flow Title=Multiple
Number of Profiles=7
Profile Names=10-year,25-year,50-year,1pct_min,100-year,1pct_plu,500-year
River Rch & RM= Stream0118,Reach-1,8728
    1537    2670    3762    2555    5098   10172    9267
Boundary for River Rch & Prof#=Stream0118,Reach-1,1
Up Type=0
Dn Type=3
Dn Slope=0.005
Boundary for River Rch & Prof#=Stream0118,Reach-1,2
Up Type=0
Dn Type=3
Dn Slope=0.005
Boundary for River Rch & Prof#=Stream0118,Reach-1,3
Up Type=0
Dn Type=3
Dn Slope=0.005
Boundary for River Rch & Prof#=Stream0118,Reach-1,4
Up Type=0
Dn Type=3
Dn Slope=0.005
Boundary for River Rch & Prof#=Stream0118,Reach-1,5
Up Type=0
Dn Type=3
Dn Slope=0.005
Boundary for River Rch & Prof#=Stream0118,Reach-1,6
Up Type=0
Dn Type=3
Dn Slope=0.005
Boundary for River Rch & Prof#=Stream0118,Reach-1,7
Up Type=0
Dn Type=3
Dn Slope=0.005

--- Stream0118.g01 (geometry) ---

Geom Title=Existing Conditions

River Reach=Stream0118,Reach-1
Reach XY= 30
      1775625.00     13933475.00      1775722.04     13933533.14
      1775727.25     13933669.06      1775822.76     13933830.93
      1775828.75     13934123.45      1776069.17     13934422.70
      1776272.75     13934880.93      1776277.27     13935019.06
      1776324.48     13935090.22      1776326.22     13935414.50
      1776374.93     13935495.03      1776388.37     13936138.32
      1776908.33     13936658.35      1777218.95     13936866.84
      1777630.93     13937072.75      1777769.06     13937077.27
      1777971.78     13937166.71      1778031.67     13937134.30
      1778326.47     13937371.45      1778664.49     13937423.79
      1779225.10     13937232.32      1779385.00     13937335.65
      1779619.48     13937622.57      1779732.86     13937981.17
      1779897.87     13938198.84      1780015.82     13938268.05
      1779983.25     13938328.22      1780180.85     13938727.29
      1780271.38     13938826.50      1780375.00     13939175.00

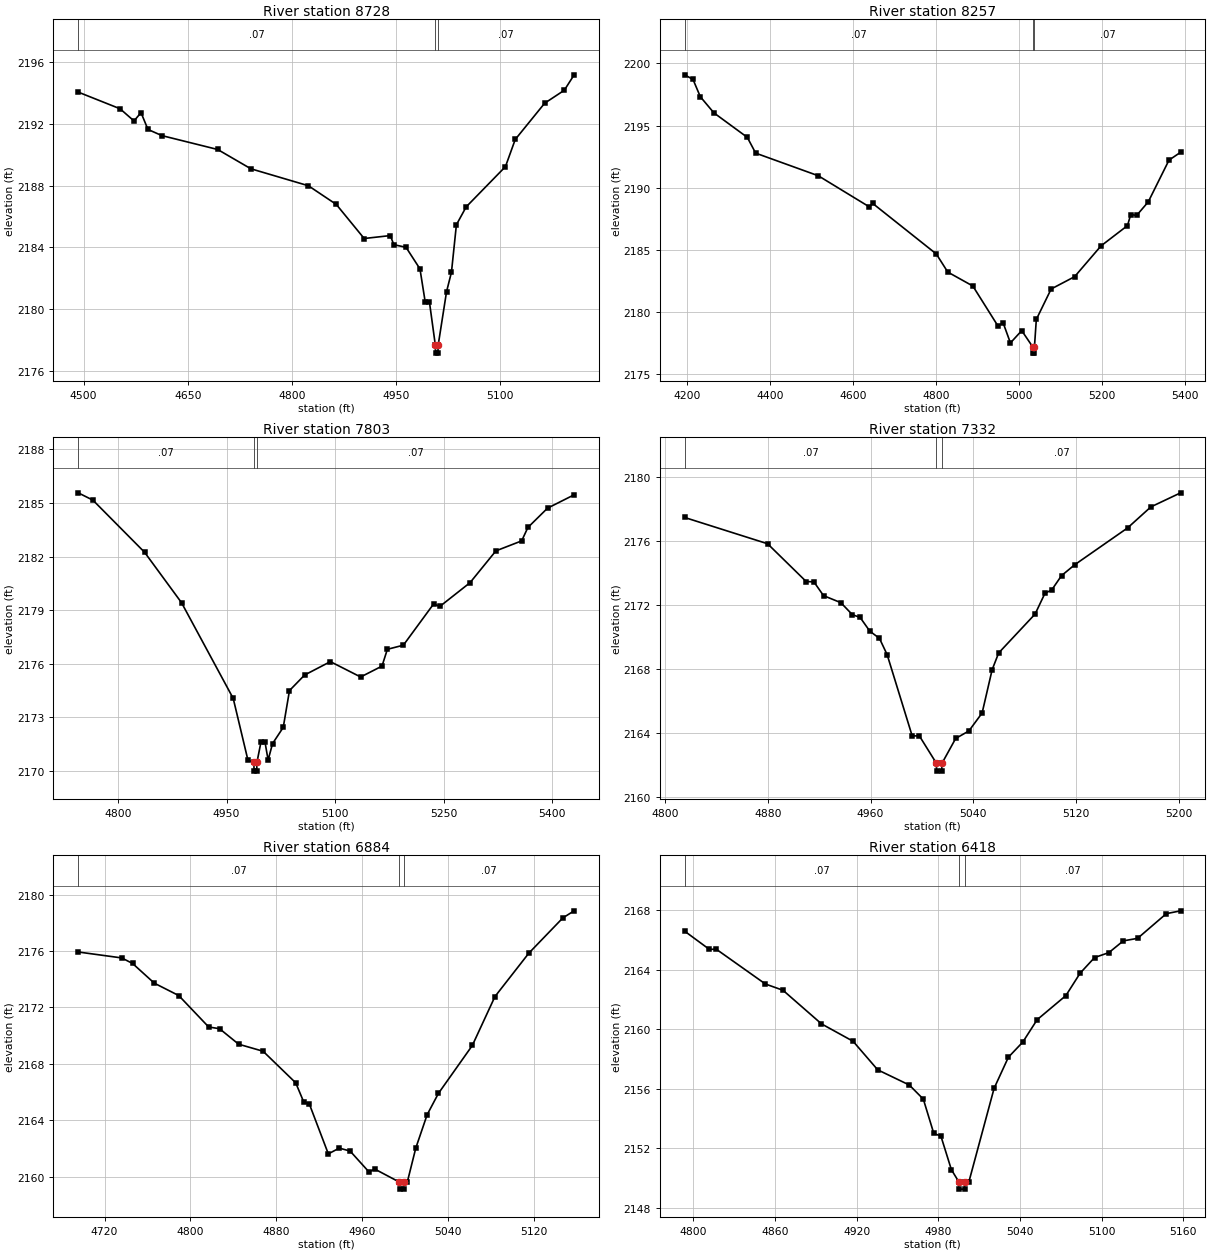
Type RM Length L Ch R = 1,8728,471,471,471
BEGIN DESCRIPTION:
Stream0118 18.0
END DESCRIPTION:
XS GIS Cut Line= 3
      1775174.96     13933475.00      1775675.00     13933525.00
      1775825.03     13933374.97
#Sta/Elev= 30
  4492.2 2194.07  4552.5 2192.99  4572.6 2192.20  4582.7 2192.74  4592.7 2191.65
  4612.8 2191.25  4693.2 2190.35  4741.0 2189.10  4823.9 2188.00  4864.1 2186.79
  4904.3 2184.58  4942.0 2184.77  4947.0 2184.18  4964.6 2184.01  4984.7 2182.61
  4992.2 2180.48  4998.3 2180.48  5006.9 2177.65  5007.1 2177.15  5010.6 2177.15
  5010.9 2177.65  5023.0 2181.13  5030.1 2182.40  5037.2 2185.47  5051.3 2186.63
  5107.9 2189.24  5122.0 2191.00  5164.4 2193.35  5192.7 2194.19  5206.9 2195.19
#Mann=3,-1,0
  4492.2    0.07       0  5006.9    0.05       0  5010.9    0.07       0
Bank Sta=5006.9,5010.9
Exp/Cntr=0.3,0.1

Type RM Length L Ch R = 1,8257,454,454,454
BEGIN DESCRIPTION:
Stream0118 17.0
END DESCRIPTION:
XS GIS Cut Line= 3
      1775025.04     13933825.01      1775825.00     13933925.00
      1776075.00     13933625.00
#Sta/Elev= 30
  4193.7 2199.08  4213.8 2198.71  4231.4 2197.32  4264.2 2196.02  4344.8 2194.05
  4365.0 2192.78  4516.1 2190.96  4639.6 2188.45  4647.2 2188.74  4800.8 2184.67
  4828.6 2183.21  4889.0 2182.09  4949.5 2178.88  4962.1 2179.13  4979.7 2177.51
  5007.0 2178.50  5033.6 2177.19  5033.9 2176.69  5037.5 2176.69  5037.7 2177.19
  5042.2 2179.40  5078.0 2181.85  5134.6 2182.84  5198.4 2185.32  5262.2 2186.95
  5270.0 2187.84  5284.3 2187.77  5312.3 2188.86  5362.4 2192.22  5390.4 2192.85
#Mann=3,-1,0
  4193.7    0.07       0  5033.6    0.05       0  5037.7    0.07       0
Bank Sta=5033.6,5037.7
Exp/Cntr=0.3,0.1

Type RM Length L Ch R = 1,7803,471,471,471
BEGIN DESCRIPTION:
Stream0118 16.0
END DESCRIPTION:
XS GIS Cut Line= 3
      1775725.05     13934374.99      1775975.00     13934325.00
      1776224.99     13933975.02
#Sta/Elev= 30
  4745.1 2185.57  4765.4 2185.16  4836.8 2182.24  4887.8 2179.42  4959.2 2174.06
  4979.6 2170.59  4987.7 2170.49  4988.0 2169.99  4991.7 2169.99  4992.0 2170.49
  4997.5 2171.61  5003.1 2171.61  5007.4 2170.61  5013.5 2171.53  5028.3 2172.44
  5036.9 2174.50  5057.8 2175.37  5093.4 2176.12  5135.2 2175.26  5164.7 2175.87
  5172.1 2176.81  5194.2 2177.04  5236.0 2179.35  5244.6 2179.21  5286.3 2180.54
  5322.0 2182.32  5357.6 2182.88  5366.2 2183.63  5393.3 2184.71  5430.1 2185.46
#Mann=3,-1,0
  4745.1    0.07       0  4987.7    0.05       0  4992.0    0.07       0
Bank Sta=4987.7,4992
Exp/Cntr=0.3,0.1

Type RM Length L Ch R = 1,7332,448,448,448
BEGIN DESCRIPTION:
Stream0118 15.0
END DESCRIPTION:
XS GIS Cut Line= 3
      1776024.98     13934825.02      1776175.00     13934725.00
      1776375.04     13934674.99
#Sta/Elev= 30
  4815.1 2177.47  4879.7 2175.83  4909.8 2173.47  4915.8 2173.45  4923.3 2172.59
  4936.8 2172.15  4945.8 2171.40  4951.8 2171.23  4959.4 2170.37  4966.9 2169.92
  4972.9 2168.90  4992.4 2163.83  4998.0 2163.83  5011.2 2162.13  5011.5 2161.63
  5015.4 2161.63  5015.7 2162.13  5026.3 2163.67  5036.6 2164.14  5046.9 2165.26
  5054.7 2167.96  5059.8 2169.01  5088.2 2171.44  5095.9 2172.74  5101.1 2172.94
  5108.8 2173.84  5119.1 2174.52  5160.3 2176.82  5178.4 2178.13  5201.6 2179.01
#Mann=3,-1,0
  4815.1    0.07       0  5011.2    0.05       0  5015.7    0.07       0
Bank Sta=5011.2,5015.7
Exp/Cntr=0.3,0.1

Type RM Length L Ch R = 1,6884,466,466,466
BEGIN DESCRIPTION:
Stream0118 14.0
END DESCRIPTION:
XS GIS Cut Line= 3
      1776025.05     13935075.01      1776325.00     13935125.00
      1776475.00     13935075.00
#Sta/Elev= 30
  4695.5 2175.93  4736.0 2175.51  4746.1 2175.12  4766.4 2173.72  4789.2 2172.84
  4817.1 2170.61  4827.2 2170.49  4845.0 2169.39  4867.8 2168.89  4898.2 2166.65
  4905.8 2165.27  4910.9 2165.15  4928.6 2161.61  4938.8 2162.02  4948.9 2161.81
  4966.6 2160.32  4971.7 2160.54  4994.8 2159.61  4995.1 2159.11  4999.0 2159.11
  4999.4 2159.61  5002.2 2159.61  5010.1 2162.02  5020.7 2164.39  5031.2 2165.90
  5062.8 2169.30  5083.9 2172.77  5115.5 2175.85  5147.2 2178.35  5157.7 2178.85
#Mann=3,-1,0
  4695.5    0.07       0  4994.8    0.05       0  4999.4    0.07       0
Bank Sta=4994.8,4999.4
Exp/Cntr=0.3,0.1

Type RM Length L Ch R = 1,6418,500,500,500
BEGIN DESCRIPTION:
Stream0118 13.0
END DESCRIPTION:
XS GIS Cut Line= 3
      1776174.95     13935524.99      1776375.00     13935575.00
      1776524.99     13935525.00
#Sta/Elev= 30
  4793.7 2166.60  4811.8 2165.38  4816.9 2165.39  4853.0 2163.05  4865.9 2162.63
  4894.2 2160.37  4917.4 2159.20  4935.5 2157.28  4958.7 2156.26  4969.0 2155.31
  4976.7 2153.00  4981.9 2152.83  4989.6 2150.57  4995.0 2149.76  4995.3 2149.26
  4999.3 2149.26  4999.6 2149.76  5002.5 2149.76  5021.0 2156.04  5031.5 2158.13
  5042.1 2159.15  5052.6 2160.65  5073.7 2162.27  5084.2 2163.78  5094.8 2164.83
  5105.3 2165.16  5115.9 2165.95  5126.4 2166.12  5147.5 2167.78  5158.0 2167.97
#Mann=3,-1,0
  4793.7    0.07       0  4995.0    0.05       0  4999.6    0.07       0
Bank Sta=4995,4999.6
Exp/Cntr=0.3,0.1

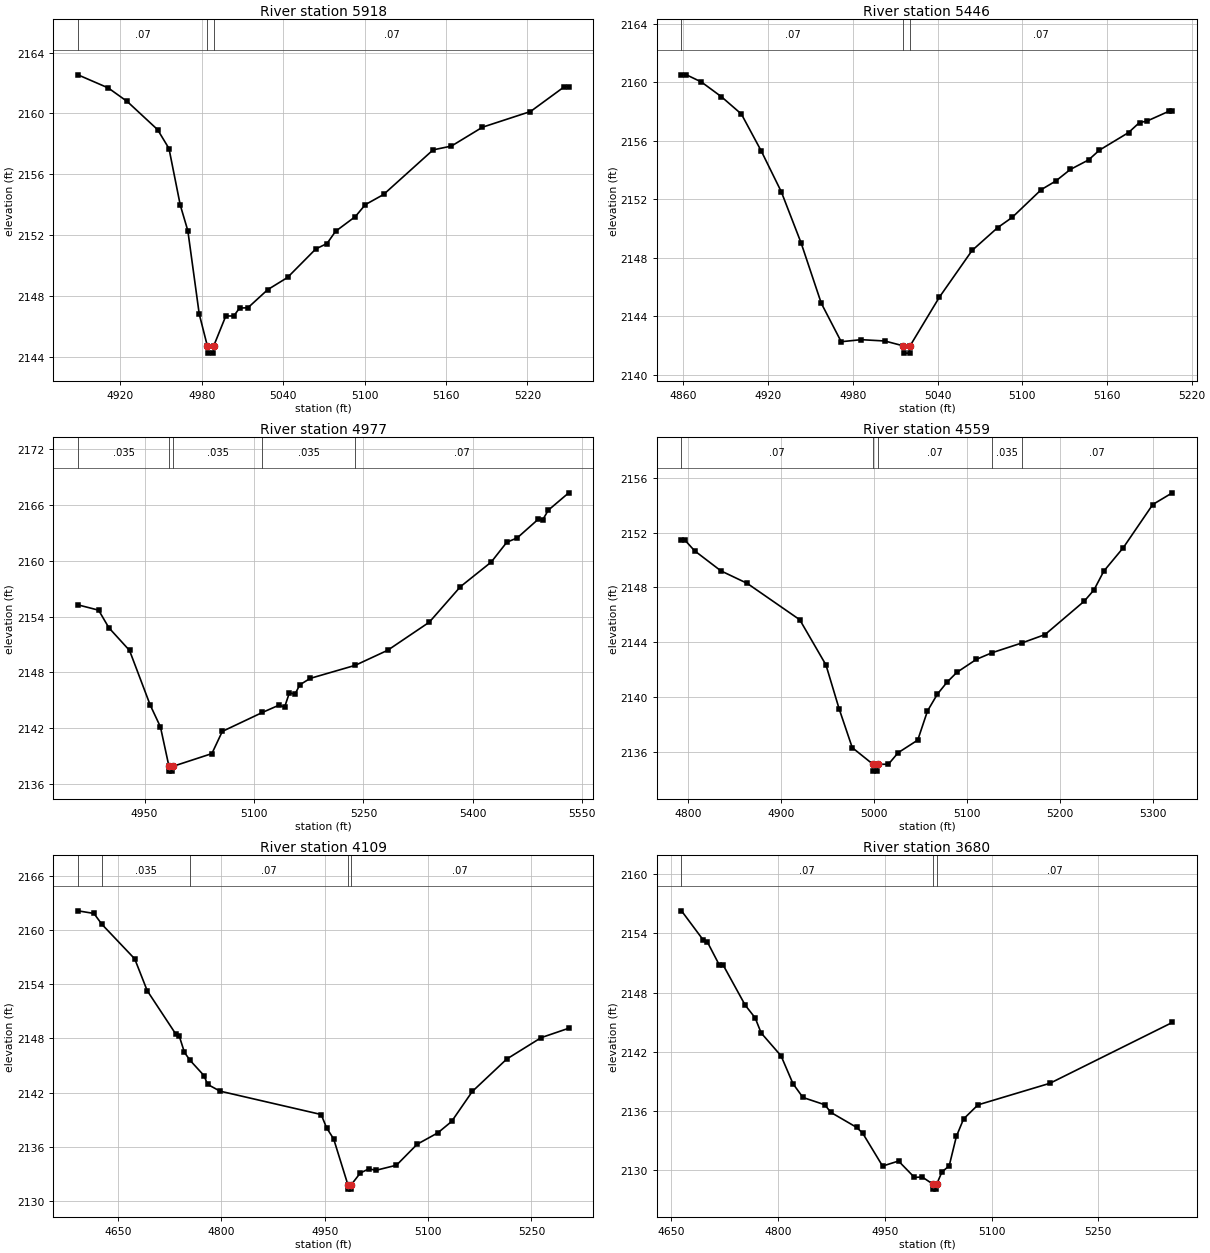
Type RM Length L Ch R = 1,5918,472,472,472
BEGIN DESCRIPTION:
Stream0118 12.0
END DESCRIPTION:
XS GIS Cut Line= 3
      1776275.03     13936124.99      1776375.00     13936075.00
      1776575.02     13935924.98
#Sta/Elev= 30
  4888.7 2162.54  4911.0 2161.68  4925.0 2160.79  4947.4 2158.94  4955.8 2157.70
  4964.1 2153.99  4969.7 2152.30  4978.1 2146.83  4984.0 2144.76  4984.4 2144.26
  4988.5 2144.26  4988.9 2144.76  4997.7 2146.70  5003.6 2146.70  5007.8 2147.22
  5014.0 2147.24  5028.6 2148.43  5043.2 2149.23  5064.0 2151.10  5072.3 2151.46
  5078.6 2152.26  5093.2 2153.23  5100.5 2154.01  5114.0 2154.68  5150.5 2157.61
  5164.0 2157.86  5186.9 2159.10  5222.3 2160.13  5247.3 2161.76  5250.5 2161.76
#Mann=3,-1,0
  4888.7    0.07       0  4984.0    0.05       0  4988.9    0.07       0
Bank Sta=4984,4988.9
Exp/Cntr=0.3,0.1

Type RM Length L Ch R = 1,5446,469,469,469
BEGIN DESCRIPTION:
Stream0118 11.0
END DESCRIPTION:
XS GIS Cut Line= 3
      1776575.00     13936525.00      1776675.00     13936425.00
      1776725.01     13936224.97
#Sta/Elev= 30
  4858.6 2160.50  4862.1 2160.50  4872.7 2160.01  4886.9 2159.00  4901.0 2157.82
  4915.2 2155.27  4929.3 2152.50  4943.4 2148.98  4957.6 2144.88  4971.7 2142.25
  4985.9 2142.39  5002.6 2142.30  5015.6 2141.97  5016.0 2141.47  5020.2 2141.47
  5020.5 2141.97  5041.2 2145.29  5064.4 2148.49  5082.5 2150.05  5092.8 2150.75
  5113.4 2152.65  5123.7 2153.24  5134.0 2154.03  5146.9 2154.68  5154.6 2155.35
  5175.2 2156.55  5183.0 2157.24  5188.1 2157.33  5203.6 2158.00  5206.2 2158.00
#Mann=3,-1,0
  4858.6    0.07       0  5015.6    0.05       0  5020.5    0.07       0
Bank Sta=5015.6,5020.5
Exp/Cntr=0.3,0.1

Type RM Length L Ch R = 1,4977,418,418,418
BEGIN DESCRIPTION:
Stream0118 10.0
END DESCRIPTION:
XS GIS Cut Line= 3
      1776925.02     13936824.98      1777025.00     13936725.00
      1777375.00     13936325.01
#Sta/Elev= 30
  4858.6 2155.25  4886.9 2154.68  4901.0 2152.79  4929.3 2150.36  4957.6 2144.51
  4971.7 2142.15  4983.4 2137.91  4983.8 2137.41  4988.0 2137.41  4988.3 2137.91
  5042.2 2139.29  5056.5 2141.67  5111.6 2143.71  5134.3 2144.49  5141.9 2144.27
  5148.5 2145.82  5156.1 2145.66  5162.8 2146.67  5177.0 2147.36  5238.7 2148.76
  5283.3 2150.38  5340.3 2153.39  5383.0 2157.20  5425.2 2159.84  5446.6 2161.97
  5460.8 2162.43  5489.3 2164.41  5495.9 2164.39  5503.5 2165.41  5531.5 2167.27
#Mann=5,-1,0
  4858.6   0.035       0  4983.4    0.05       0  4988.3   0.035       0
  5111.6   0.035       0  5238.7    0.07       0
Bank Sta=4983.4,4988.3
Exp/Cntr=0.3,0.1

Type RM Length L Ch R = 1,4559,450,450,450
BEGIN DESCRIPTION:
Stream0118 9.0
END DESCRIPTION:
XS GIS Cut Line= 3
      1777225.01     13937074.99      1777375.00     13936925.00
      1777474.99     13936625.04
#Sta/Elev= 30
  4792.9 2151.46  4796.4 2151.46  4807.0 2150.67  4835.3 2149.21  4863.6 2148.30
  4920.2 2145.65  4948.4 2142.36  4962.6 2139.16  4976.7 2136.34  4999.0 2135.13
  4999.3 2134.63  5003.6 2134.63  5004.0 2135.13  5015.6 2135.13  5026.1 2135.97
  5047.2 2136.89  5057.7 2139.01  5068.3 2140.23  5078.8 2141.11  5089.3 2141.82
  5110.4 2142.77  5127.2 2143.25  5159.7 2143.97  5184.2 2144.57  5226.4 2147.00
  5236.9 2147.82  5247.5 2149.19  5268.5 2150.90  5300.2 2154.04  5321.2 2154.89
#Mann=5,-1,0
  4792.9    0.07       0  4999.0    0.05       0  5004.0    0.07       0
  5127.2   0.035       0  5159.7    0.07       0
Bank Sta=4999,5004
Exp/Cntr=0.3,0.1

Type RM Length L Ch R = 1,4109,429,429,429
BEGIN DESCRIPTION:
Stream0118 8.0
END DESCRIPTION:
XS GIS Cut Line= 3
      1777675.01     13937474.98      1777775.00     13937075.00
      1777775.00     13936774.99
#Sta/Elev= 30
  4591.9 2162.13  4615.1 2161.84  4626.6 2160.64  4674.3 2156.81  4692.4 2153.29
  4733.6 2148.52  4738.8 2148.29  4746.5 2146.45  4754.7 2145.57  4774.8 2143.89
  4780.0 2142.92  4798.0 2142.17  4944.9 2139.58  4952.7 2138.11  4963.0 2136.88
  4983.6 2131.82  4984.0 2131.32  4988.3 2131.32  4988.7 2131.82  5001.6 2133.10
  5014.2 2133.57  5024.2 2133.40  5054.2 2133.97  5084.2 2136.29  5114.2 2137.55
  5134.2 2138.81  5164.2 2142.13  5214.2 2145.72  5264.2 2148.09  5304.2 2149.13
#Mann=5,-1,0
  4591.9    0.07       0  4626.6   0.035       0  4754.7    0.07       0
  4983.6    0.05       0  4988.7    0.07       0
Bank Sta=4983.6,4988.7
Exp/Cntr=0.3,0.1

Type RM Length L Ch R = 1,3680,474,474,474
BEGIN DESCRIPTION:
Stream0118 7.0
END DESCRIPTION:
XS GIS Cut Line= 3
      1777975.00     13937525.00      1778125.00     13937225.00
      1778074.99     13936874.96
#Sta/Elev= 30
  4664.8 2156.30  4695.5 2153.32  4701.1 2153.14  4717.9 2150.80  4723.5 2150.77
  4754.2 2146.73  4768.2 2145.44  4776.6 2143.91  4804.6 2141.58  4821.3 2138.76
  4835.3 2137.36  4866.0 2136.62  4874.4 2135.85  4910.8 2134.32  4919.2 2133.73
  4947.1 2130.40  4969.5 2130.91  4991.8 2129.25  5002.7 2129.29  5017.9 2128.56
  5018.3 2128.06  5022.6 2128.06  5023.0 2128.56  5030.5 2129.81  5040.6 2130.42
  5050.7 2133.41  5060.8 2135.18  5081.0 2136.61  5182.0 2138.80  5353.8 2144.97
#Mann=3,-1,0
  4664.8    0.07       0  5017.9    0.05       0  5023.0    0.07       0
Bank Sta=5017.9,5023
Exp/Cntr=0.3,0.1

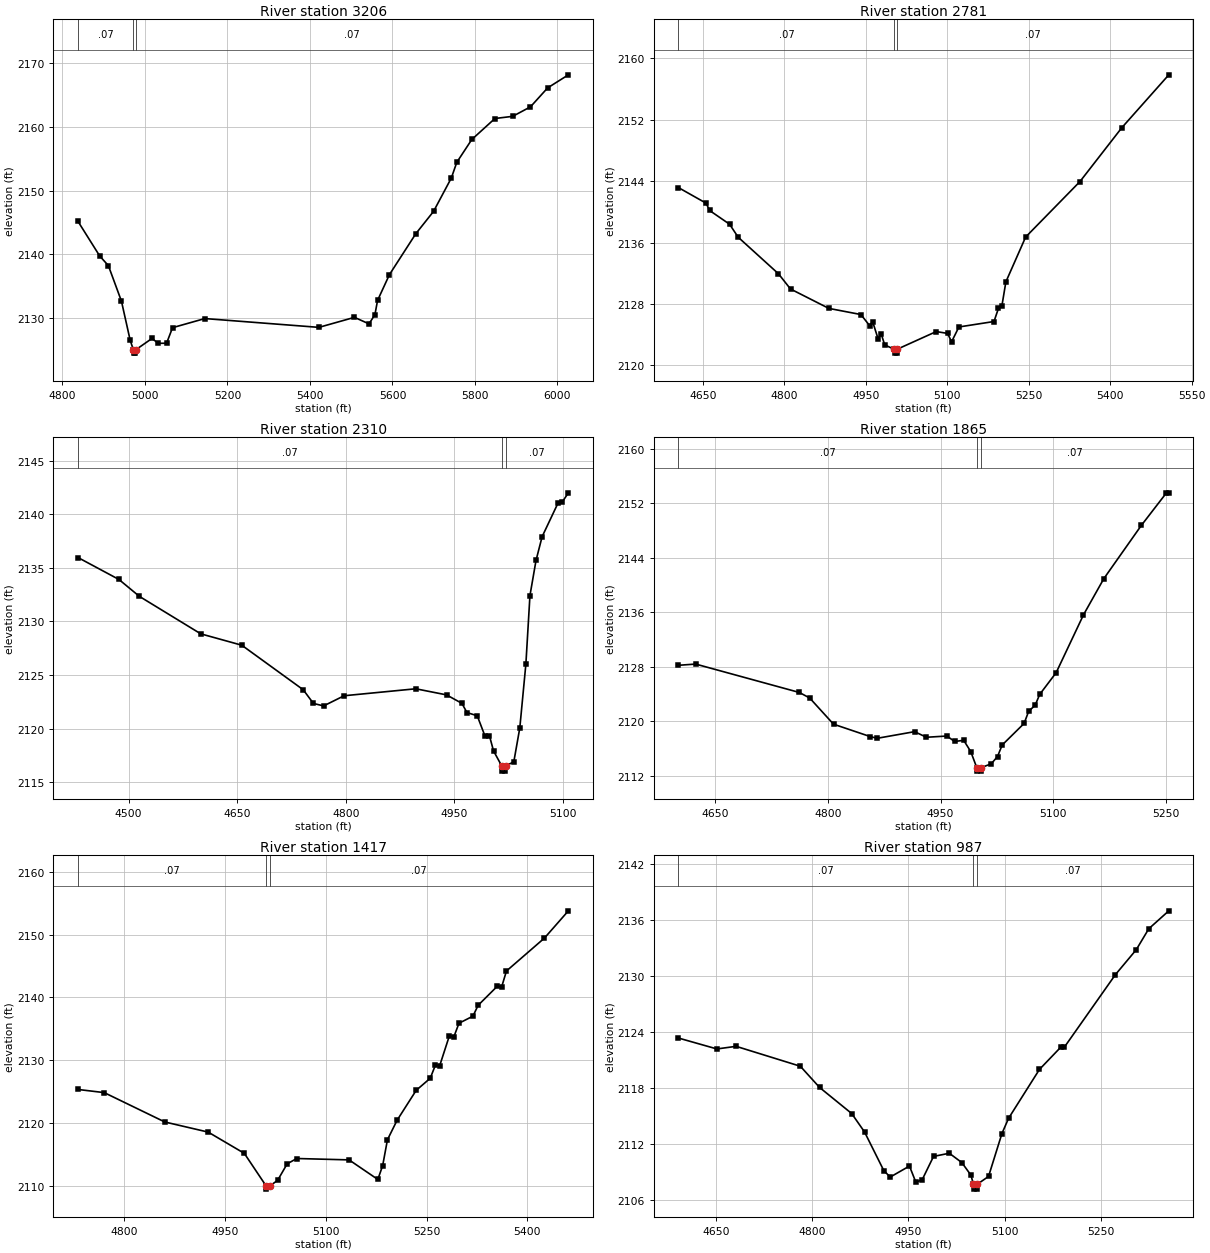
Type RM Length L Ch R = 1,3206,425,425,425
BEGIN DESCRIPTION:
Stream0118 6.0
END DESCRIPTION:
XS GIS Cut Line= 3
      1778474.98     13937575.05      1778525.00     13937425.00
      1779174.98     13936625.03
#Sta/Elev= 30
  4837.5 2145.19  4890.3 2139.75  4911.3 2138.24  4943.0 2132.66  4964.0 2126.57
  4972.0 2125.02  4972.4 2124.52  4976.7 2124.52  4977.1 2125.02  5017.2 2126.83
  5031.6 2126.06  5052.4 2126.07  5066.8 2128.51  5145.1 2129.94  5421.6 2128.56
  5507.8 2130.13  5543.0 2129.11  5557.4 2130.55  5563.8 2132.78  5592.6 2136.83
  5656.5 2143.24  5699.6 2146.75  5742.7 2151.99  5755.9 2154.44  5792.3 2158.02
  5848.3 2161.31  5891.4 2161.65  5934.5 2163.14  5976.1 2166.11  6026.4 2168.16
#Mann=3,-1,0
  4837.5    0.07       0  4972.0    0.05       0  4977.1    0.07       0
Bank Sta=4972,4977.1
Exp/Cntr=0.3,0.1

Type RM Length L Ch R = 1,2781,471,471,471
BEGIN DESCRIPTION:
Stream0118 5.0
END DESCRIPTION:
XS GIS Cut Line= 3
      1778725.02     13937674.96      1778925.00     13937325.00
      1779225.02     13936924.97
#Sta/Elev= 30
  4604.8 2143.18  4655.9 2141.14  4662.3 2140.19  4699.1 2138.40  4714.9 2136.71
  4789.0 2131.95  4811.3 2129.96  4881.9 2127.43  4940.9 2126.63  4956.8 2125.20
  4962.5 2125.71  4972.6 2123.46  4978.4 2124.08  4984.8 2122.67  5002.4 2122.10
  5002.8 2121.60  5007.2 2121.60  5007.5 2122.10  5079.7 2124.41  5100.6 2124.17
  5107.9 2123.07  5121.4 2125.01  5186.0 2125.72  5194.3 2127.45  5200.6 2127.77
  5207.9 2130.89  5244.3 2136.73  5344.3 2143.96  5421.4 2150.98  5507.9 2157.87
#Mann=3,-1,0
  4604.8    0.07       0  5002.4    0.05       0  5007.5    0.07       0
Bank Sta=5002.4,5007.5
Exp/Cntr=0.3,0.1

Type RM Length L Ch R = 1,2310,445,445,445
BEGIN DESCRIPTION:
Stream0118 4.0
END DESCRIPTION:
XS GIS Cut Line= 3
      1778924.98     13937725.02      1779325.00     13937325.00
      1779374.99     13937225.02
#Sta/Elev= 30
  4429.9 2135.97  4486.5 2133.92  4514.8 2132.34  4599.6 2128.84  4656.2 2127.78
  4741.1 2123.62  4755.2 2122.34  4769.3 2122.11  4797.6 2123.06  4896.6 2123.71
  4939.1 2123.14  4960.3 2122.35  4967.3 2121.49  4981.5 2121.19  4992.1 2119.31
  4998.4 2119.31  5004.0 2117.91  5015.2 2116.52  5015.7 2116.02  5020.3 2116.02
  5020.7 2116.52  5032.0 2116.88  5040.3 2120.06  5048.7 2126.03  5054.3 2132.41
  5062.7 2135.70  5071.1 2137.91  5093.4 2141.10  5099.0 2141.16  5107.4 2142.01
#Mann=3,-1,0
  4429.9    0.07       0  5015.2    0.05       0  5020.7    0.07       0
Bank Sta=5015.2,5020.7
Exp/Cntr=0.3,0.1

Type RM Length L Ch R = 1,1865,448,448,448
BEGIN DESCRIPTION:
Stream0118 3.0
END DESCRIPTION:
XS GIS Cut Line= 3
      1779275.03     13937824.98      1779625.00     13937625.00
      1779825.02     13937474.99
#Sta/Elev= 30
  4600.9 2128.21  4623.9 2128.39  4762.1 2124.22  4775.8 2123.41  4807.5 2119.57
  4856.4 2117.75  4865.8 2117.50  4915.4 2118.47  4931.3 2117.65  4958.6 2117.83
  4968.7 2117.03  4980.9 2117.20  4990.3 2115.54  4998.3 2113.18  4998.8 2112.68
  5003.4 2112.68  5003.8 2113.18  5017.5 2113.75  5025.9 2114.82  5032.1 2116.51
  5061.3 2119.68  5067.5 2121.49  5075.9 2122.32  5082.1 2123.94  5104.0 2127.13
  5140.4 2135.62  5167.5 2140.93  5217.5 2148.75  5250.9 2153.52  5254.0 2153.52
#Mann=3,-1,0
  4600.9    0.07       0  4998.3    0.05       0  5003.8    0.07       0
Bank Sta=4998.3,5003.8
Exp/Cntr=0.3,0.1

Type RM Length L Ch R = 1,1417,430,430,430
BEGIN DESCRIPTION:
Stream0118 2.0
END DESCRIPTION:
XS GIS Cut Line= 3
      1779524.99     13938125.00      1779775.00     13938025.00
      1780124.97     13937725.03
#Sta/Elev= 30
  4731.0 2125.37  4770.1 2124.87  4860.3 2120.20  4924.9 2118.59  4978.7 2115.21
  5011.2 2110.02  5011.6 2109.52  5016.7 2110.02  5028.3 2110.92  5042.5 2113.54
  5056.8 2114.39  5134.7 2114.17  5177.5 2111.06  5184.7 2113.26  5191.8 2117.37
  5206.1 2120.46  5234.6 2125.23  5255.5 2127.15  5263.1 2129.21  5269.7 2129.18
  5284.0 2133.90  5290.6 2133.71  5298.3 2135.90  5319.1 2137.03  5326.8 2138.75
  5355.3 2141.78  5361.9 2141.70  5369.0 2144.21  5425.6 2149.45  5461.2 2153.78
#Mann=3,-1,0
  4731.0    0.07       0  5011.2    0.05       0  5016.7    0.07       0
Bank Sta=5011.2,5016.7
Exp/Cntr=0.3,0.1

Type RM Length L Ch R = 1,987,282,282,282
BEGIN DESCRIPTION:
Stream0118 1.0
END DESCRIPTION:
XS GIS Cut Line= 3
      1779574.99     13938325.00      1779975.00     13938325.00
      1780324.98     13938225.00
#Sta/Elev= 30
  4591.5 2123.37  4651.5 2122.20  4681.5 2122.48  4781.5 2120.35  4811.5 2118.08
  4861.5 2115.29  4881.5 2113.32  4911.5 2109.19  4921.5 2108.49  4951.5 2109.67
  4961.5 2107.93  4971.5 2108.23  4989.0 2110.70  5013.6 2111.04  5033.1 2110.04
  5047.4 2108.68  5051.1 2107.70  5051.6 2107.20  5056.3 2107.20  5056.7 2107.70
  5074.7 2108.56  5095.5 2113.14  5105.9 2114.78  5154.0 2120.01  5187.8 2122.43
  5193.0 2122.41  5272.3 2130.15  5304.8 2132.82  5324.3 2135.06  5355.5 2136.98
#Mann=3,-1,0
  4591.5    0.07       0  5051.1    0.05       0  5056.7    0.07       0
Bank Sta=5051.1,5056.7
Exp/Cntr=0.3,0.1

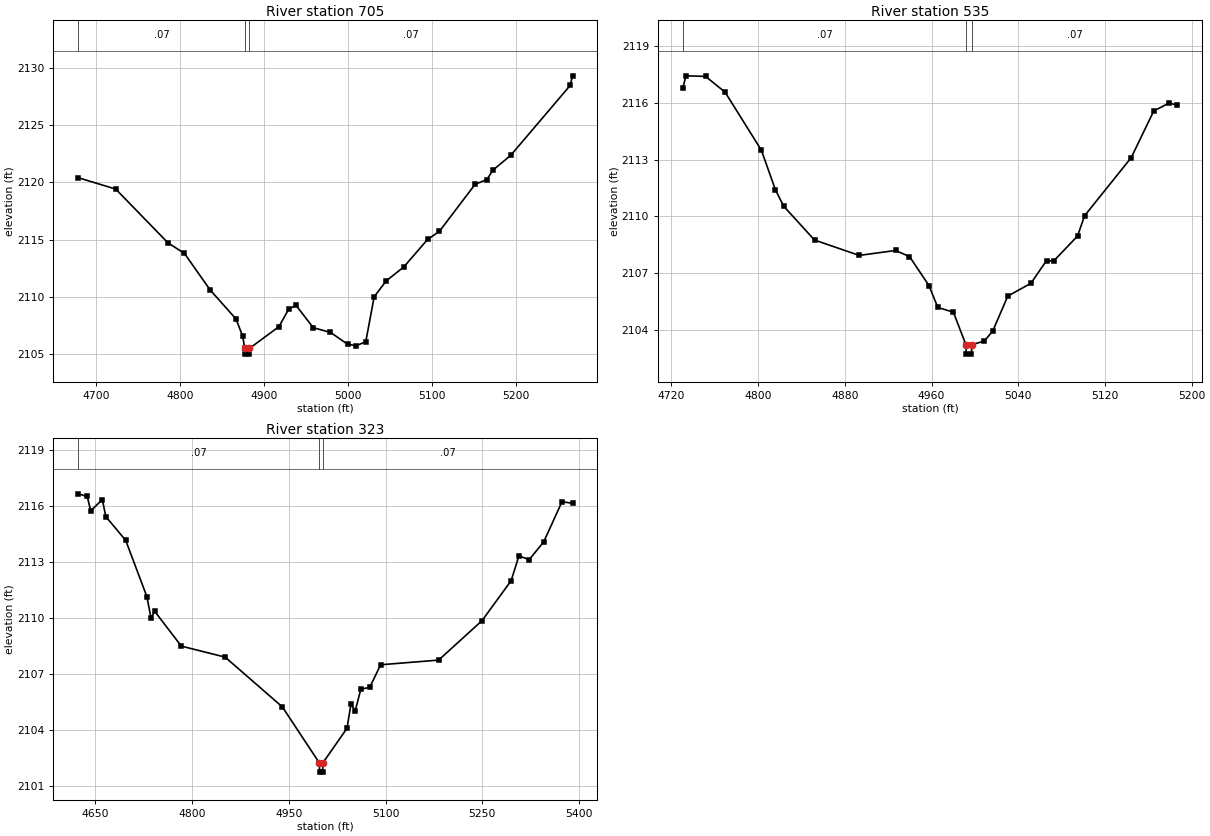
Type RM Length L Ch R = 1,705,170,170,170
BEGIN DESCRIPTION:
Stream0118 0.0
END DESCRIPTION:
XS GIS Cut Line= 3
      1779811.13     13938621.28      1780146.21     13938550.23
      1780323.77     13938379.73
#Sta/Elev= 30
  4679.0 2120.42  4723.8 2119.42  4785.9 2114.73  4805.6 2113.80  4836.3 2110.60
  4867.0 2108.07  4875.0 2106.55  4877.4 2105.50  4877.8 2105.00  4882.5 2105.00
  4883.0 2105.50  4918.1 2107.40  4929.8 2108.94  4938.5 2109.26  4959.0 2107.31
  4979.5 2106.90  4999.9 2105.86  5010.1 2105.74  5021.5 2106.08  5031.5 2110.01
  5045.7 2111.39  5066.8 2112.62  5095.1 2115.02  5109.2 2115.73  5151.7 2119.84
  5165.8 2120.26  5172.8 2121.07  5194.1 2122.37  5264.9 2128.48  5267.7 2129.32
#Mann=3,-1,0
  4679.0    0.07       0  4877.4    0.05       0  4883.0    0.07       0
Bank Sta=4877.4,4883
Exp/Cntr=0.3,0.1

Type RM Length L Ch R = 1,535,212,212,212
BEGIN DESCRIPTION:
Stream0118 0.1
END DESCRIPTION:
XS GIS Cut Line= 3
      1779924.73     13938790.07      1780155.64     13938732.35
      1780295.23     13938564.92
#Sta/Elev= 30
  4730.7 2116.79  4733.6 2117.41  4751.6 2117.38  4769.6 2116.55  4803.1 2113.49
  4816.0 2111.41  4823.7 2110.54  4852.1 2108.76  4893.3 2107.95  4926.8 2108.21
  4939.7 2107.89  4957.7 2106.36  4965.8 2105.21  4980.2 2104.96  4991.7 2103.25
  4992.1 2102.75  4996.8 2102.75  4997.3 2103.25  5008.8 2103.44  5016.6 2103.98
  5030.4 2105.81  5051.7 2106.48  5066.1 2107.68  5072.6 2107.65  5094.7 2108.97
  5101.2 2110.04  5144.2 2113.10  5165.0 2115.56  5179.3 2115.98  5186.7 2115.86
#Mann=3,-1,0
  4730.7    0.07       0  4991.7    0.05       0  4997.3    0.07       0
Bank Sta=4991.7,4997.3
Exp/Cntr=0.3,0.1

Type RM Length L Ch R = 1,323,0,0,0
BEGIN DESCRIPTION:
Stream0118 0.2
END DESCRIPTION:
XS GIS Cut Line= 4
      1779917.38     13938804.25      1780123.09     13938894.08
      1780322.31     13938881.06      1780629.59     13938730.03
#Sta/Elev= 30
  4623.4 2116.66  4637.5 2116.52  4642.9 2115.75  4660.9 2116.35  4666.3 2115.44
  4697.2 2114.16  4729.9 2111.15  4736.5 2109.99  4742.0 2110.36  4783.4 2108.49
  4851.3 2107.90  4940.0 2105.23  4997.3 2102.23  4997.8 2101.73  5002.5 2101.73
  5002.9 2102.23  5040.2 2104.08  5046.4 2105.37  5053.0 2105.02  5061.7 2106.18
  5075.5 2106.28  5092.4 2107.49  5182.3 2107.74  5249.7 2109.86  5294.7 2112.00
  5306.8 2113.33  5322.7 2113.13  5345.2 2114.08  5373.6 2116.24  5389.9 2116.15
#Mann=3,-1,0
  4623.4    0.07       0  4997.3    0.05       0  5002.9    0.07       0
Bank Sta=4997.3,5002.9
Exp/Cntr=0.3,0.1

Chan Stop Cuts=-1