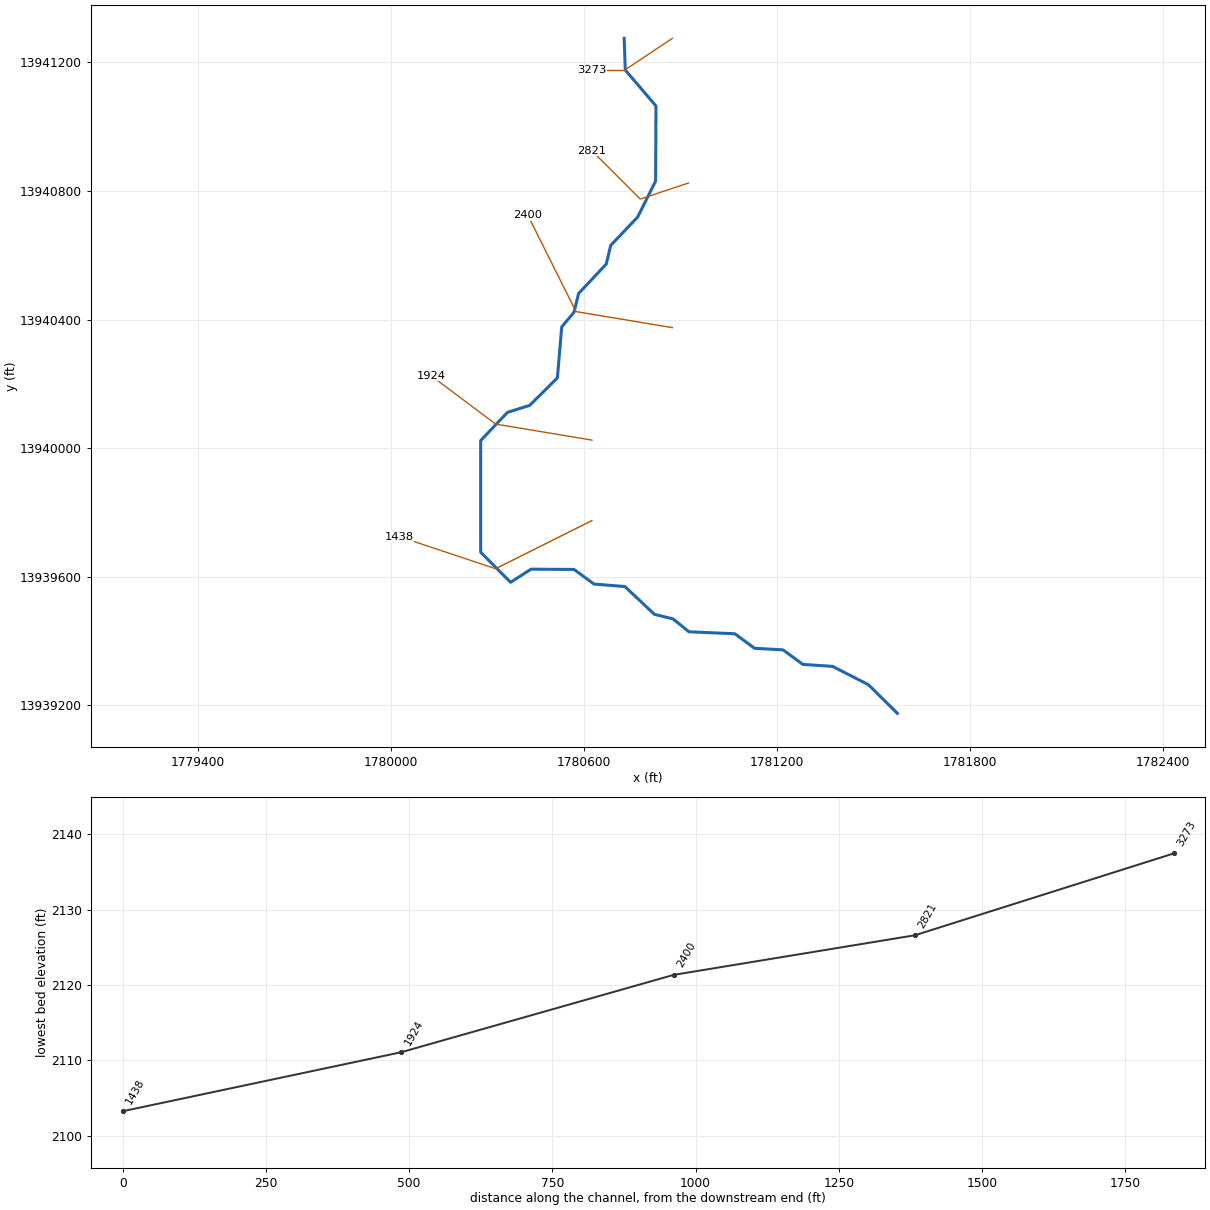
--- Stream0119.prj (project) ---

Proj Title=Stream0119 Base Level Engineering
Current Plan=p01
Default Exp/Contr=0.3,0.1
English Units
Geom File=g01
Flow File=f01
Plan File=p01
BEGIN DESCRIPTION:
Stream0119
END DESCRIPTION:

--- Stream0119.p01 (plan) ---

Plan Title=Multiple Run
Short Identifier=Multiple
Geom File=g01
Flow File=f01
Subcritical Flow
K Sum by GR= 0
Std Step Tol= 0.01
Critical Tol= 0.01
Num of Std Step Trials= 20
Max Error Tol= 0.3
Flow Tol Ratio= 0.001
Split Flow NTrial= 30
Split Flow Tol= 0.02
Split Flow Ratio= 0.02
Log Output Level= 0
Friction Slope Method= 1
Unsteady Friction Slope Method= 2
Unsteady Bridges Friction Slope Method= 1
Parabolic Critical Depth
Global Vel Dist=  1 , 1 , 1
Global Log Level= 0
CheckData=True
Encroach Param= -1, 0, 0, 0
BEGIN DESCRIPTION:
Multiple Run
END DESCRIPTION:

--- Stream0119.f01 (steady flow) ---

Flow Title=Multiple
Number of Profiles=7
Profile Names=10-year,25-year,50-year,1pct_min,100-year,1pct_plu,500-year
River Rch & RM= Stream0119,Reach-1,3273
     654    1092    1501    1000    1994    3979    3475
Boundary for River Rch & Prof#=Stream0119,Reach-1,1
Up Type=0
Dn Type=3
Dn Slope=0.005
Boundary for River Rch & Prof#=Stream0119,Reach-1,2
Up Type=0
Dn Type=3
Dn Slope=0.005
Boundary for River Rch & Prof#=Stream0119,Reach-1,3
Up Type=0
Dn Type=3
Dn Slope=0.005
Boundary for River Rch & Prof#=Stream0119,Reach-1,4
Up Type=0
Dn Type=3
Dn Slope=0.005
Boundary for River Rch & Prof#=Stream0119,Reach-1,5
Up Type=0
Dn Type=3
Dn Slope=0.005
Boundary for River Rch & Prof#=Stream0119,Reach-1,6
Up Type=0
Dn Type=3
Dn Slope=0.005
Boundary for River Rch & Prof#=Stream0119,Reach-1,7
Up Type=0
Dn Type=3
Dn Slope=0.005

--- Stream0119.g01 (geometry) ---

Geom Title=Existing Conditions

River Reach=Stream0119,Reach-1
Reach XY= 30
      1780725.00     13941275.00      1780728.39     13941176.41
      1780823.95     13941064.56      1780822.76     13940830.93
      1780766.84     13940718.95      1780683.18     13940631.04
      1780669.13     13940572.72      1780583.16     13940481.05
      1780568.86     13940422.83      1780530.71     13940377.35
      1780517.19     13940218.79      1780431.07     13940133.15
      1780361.76     13940111.38      1780278.53     13940023.55
      1780278.54     13939676.44      1780371.57     13939582.79
      1780435.44     13939623.62      1780569.06     13939622.75
      1780630.98     13939577.36      1780727.42     13939569.46
      1780818.95     13939483.16      1780877.17     13939468.86
      1780926.56     13939428.76      1781069.06     13939422.73
      1781130.98     13939377.36      1781219.03     13939372.65
      1781280.97     13939327.35      1781373.42     13939321.18
      1781484.71     13939264.30      1781575.00     13939175.00

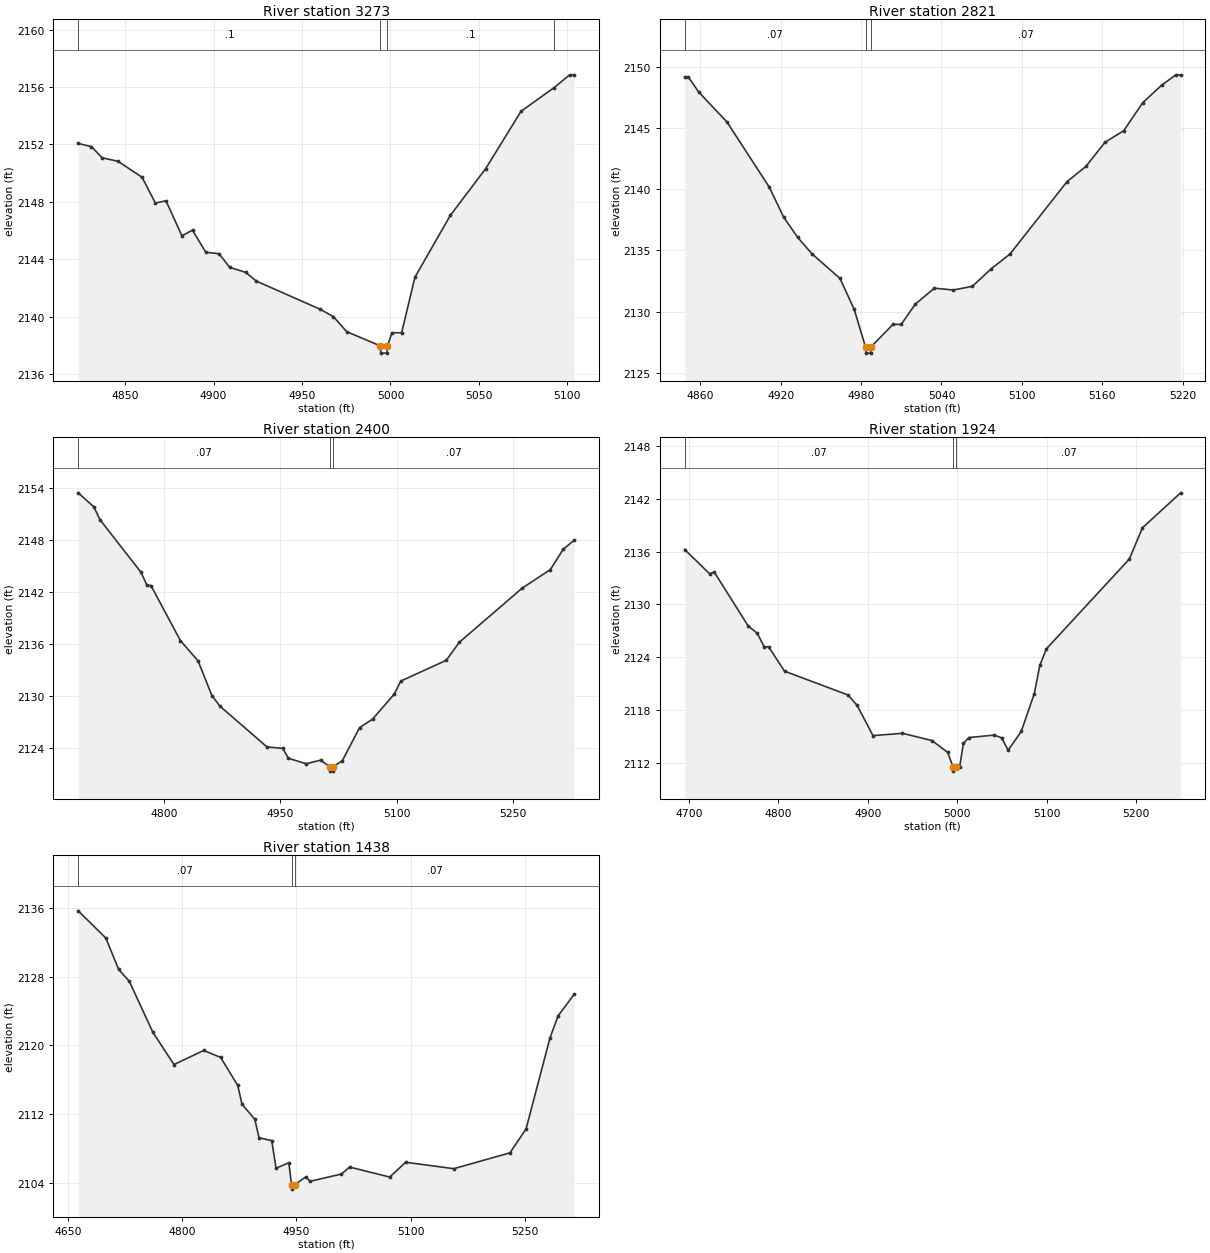
Type RM Length L Ch R = 1,3273,452,452,452
BEGIN DESCRIPTION:
Stream0119 5.0
END DESCRIPTION:
XS GIS Cut Line= 3
      1780875.01     13941275.01      1780725.00     13941175.00
      1780624.99     13941175.00
#Sta/Elev= 30
  4823.5 2152.07  4831.0 2151.84  4837.0 2151.07  4846.0 2150.82  4859.6 2149.71
  4867.1 2147.91  4873.1 2148.07  4882.1 2145.63  4888.1 2146.02  4895.6 2144.48
  4903.1 2144.38  4909.1 2143.43  4918.2 2143.08  4924.2 2142.47  4960.2 2140.51
  4967.7 2140.00  4975.2 2138.95  4994.3 2137.95  4994.5 2137.45  4998.0 2137.45
  4998.3 2137.95  5000.8 2138.87  5006.3 2138.87  5013.8 2142.74  5033.8 2147.05
  5053.8 2150.31  5073.8 2154.31  5092.5 2155.96  5101.3 2156.85  5103.8 2156.85
#Mann=4,-1,0
  4823.5     0.1       0  4994.3    0.05       0  4998.3     0.1       0
  5092.5    0.07       0
Bank Sta=4994.3,4998.3
Exp/Cntr=0.3,0.1

Type RM Length L Ch R = 1,2821,421,421,421
BEGIN DESCRIPTION:
Stream0119 4.0
END DESCRIPTION:
XS GIS Cut Line= 3
      1780924.99     13940825.00      1780775.00     13940775.00
      1780625.02     13940924.98
#Sta/Elev= 30
  4848.3 2149.19  4850.9 2149.19  4858.8 2147.94  4879.9 2145.49  4911.5 2140.16
  4922.1 2137.73  4932.6 2136.07  4943.2 2134.73  4964.2 2132.71  4974.8 2130.19
  4983.3 2127.10  4983.6 2126.60  4987.1 2126.60  4987.3 2127.10  5003.8 2128.95
  5009.9 2128.95  5020.5 2130.61  5034.7 2131.91  5048.8 2131.76  5063.0 2132.06
  5077.1 2133.49  5091.3 2134.72  5133.7 2140.62  5147.8 2141.86  5162.0 2143.83
  5176.1 2144.79  5190.2 2147.07  5204.4 2148.51  5215.0 2149.35  5218.5 2149.35
#Mann=3,-1,0
  4848.3    0.07       0  4983.3    0.05       0  4987.3    0.07       0
Bank Sta=4983.3,4987.3
Exp/Cntr=0.3,0.1

Type RM Length L Ch R = 1,2400,476,476,476
BEGIN DESCRIPTION:
Stream0119 3.0
END DESCRIPTION:
XS GIS Cut Line= 3
      1780875.04     13940374.99      1780575.00     13940425.00
      1780425.00     13940725.01
#Sta/Elev= 30
  4689.4 2153.42  4709.7 2151.79  4717.3 2150.34  4770.5 2144.25  4778.1 2142.75
  4783.2 2142.74  4821.2 2136.39  4844.0 2134.05  4861.8 2130.06  4871.9 2128.86
  4932.8 2124.14  4953.0 2123.97  4960.6 2122.83  4983.4 2122.20  5002.0 2122.61
  5013.9 2121.85  5014.2 2121.35  5017.7 2121.35  5017.9 2121.85  5029.9 2122.53
  5052.3 2126.37  5069.0 2127.34  5097.0 2130.23  5105.4 2131.73  5164.1 2134.12
  5180.8 2136.19  5261.9 2142.43  5298.2 2144.57  5315.0 2146.92  5329.0 2147.96
#Mann=3,-1,0
  4689.4    0.07       0  5013.9    0.05       0  5017.9    0.07       0
Bank Sta=5013.9,5017.9
Exp/Cntr=0.3,0.1

Type RM Length L Ch R = 1,1924,486,486,486
BEGIN DESCRIPTION:
Stream0119 2.0
END DESCRIPTION:
XS GIS Cut Line= 3
      1780625.05     13940024.99      1780325.00     13940075.00
      1780124.99     13940225.01
#Sta/Elev= 30
  4695.3 2136.23  4723.2 2133.47  4728.3 2133.68  4766.3 2127.55  4776.5 2126.72
  4784.1 2125.20  4789.1 2125.19  4806.9 2122.43  4877.8 2119.73  4888.0 2118.55
  4905.7 2115.12  4938.7 2115.38  4971.6 2114.56  4989.3 2113.21  4995.0 2111.59
  4995.2 2111.09  4999.0 2111.59  5002.6 2111.59  5006.8 2114.25  5013.0 2114.90
  5041.2 2115.18  5049.5 2114.87  5056.8 2113.46  5071.4 2115.59  5085.9 2119.86
  5092.2 2123.10  5099.5 2124.96  5192.2 2135.15  5206.8 2138.69  5249.5 2142.66
#Mann=3,-1,0
  4695.3    0.07       0  4995.0    0.05       0  4999.0    0.07       0
Bank Sta=4995,4999
Exp/Cntr=0.3,0.1

Type RM Length L Ch R = 1,1438,0,0,0
BEGIN DESCRIPTION:
Stream0119 1.0
END DESCRIPTION:
XS GIS Cut Line= 3
      1780624.98     13939774.99      1780325.00     13939625.00
      1780025.01     13939725.00
#Sta/Elev= 30
  4663.3 2135.68  4699.6 2132.51  4716.4 2128.86  4730.4 2127.48  4761.1 2121.58
  4789.1 2117.78  4828.2 2119.42  4850.5 2118.60  4872.9 2115.34  4878.5 2113.16
  4895.3 2111.40  4900.9 2109.25  4917.6 2108.92  4923.2 2105.70  4940.0 2106.34
  4943.6 2103.77  4943.8 2103.27  4947.6 2103.77  4962.4 2104.70  4967.9 2104.18
  5009.2 2105.03  5019.8 2105.84  5072.5 2104.68  5093.6 2106.40  5156.8 2105.65
  5230.6 2107.50  5251.7 2110.28  5283.3 2120.92  5293.8 2123.45  5314.9 2125.95
#Mann=3,-1,0
  4663.3    0.07       0  4943.6    0.05       0  4947.6    0.07       0
Bank Sta=4943.6,4947.6
Exp/Cntr=0.3,0.1

Chan Stop Cuts=-1