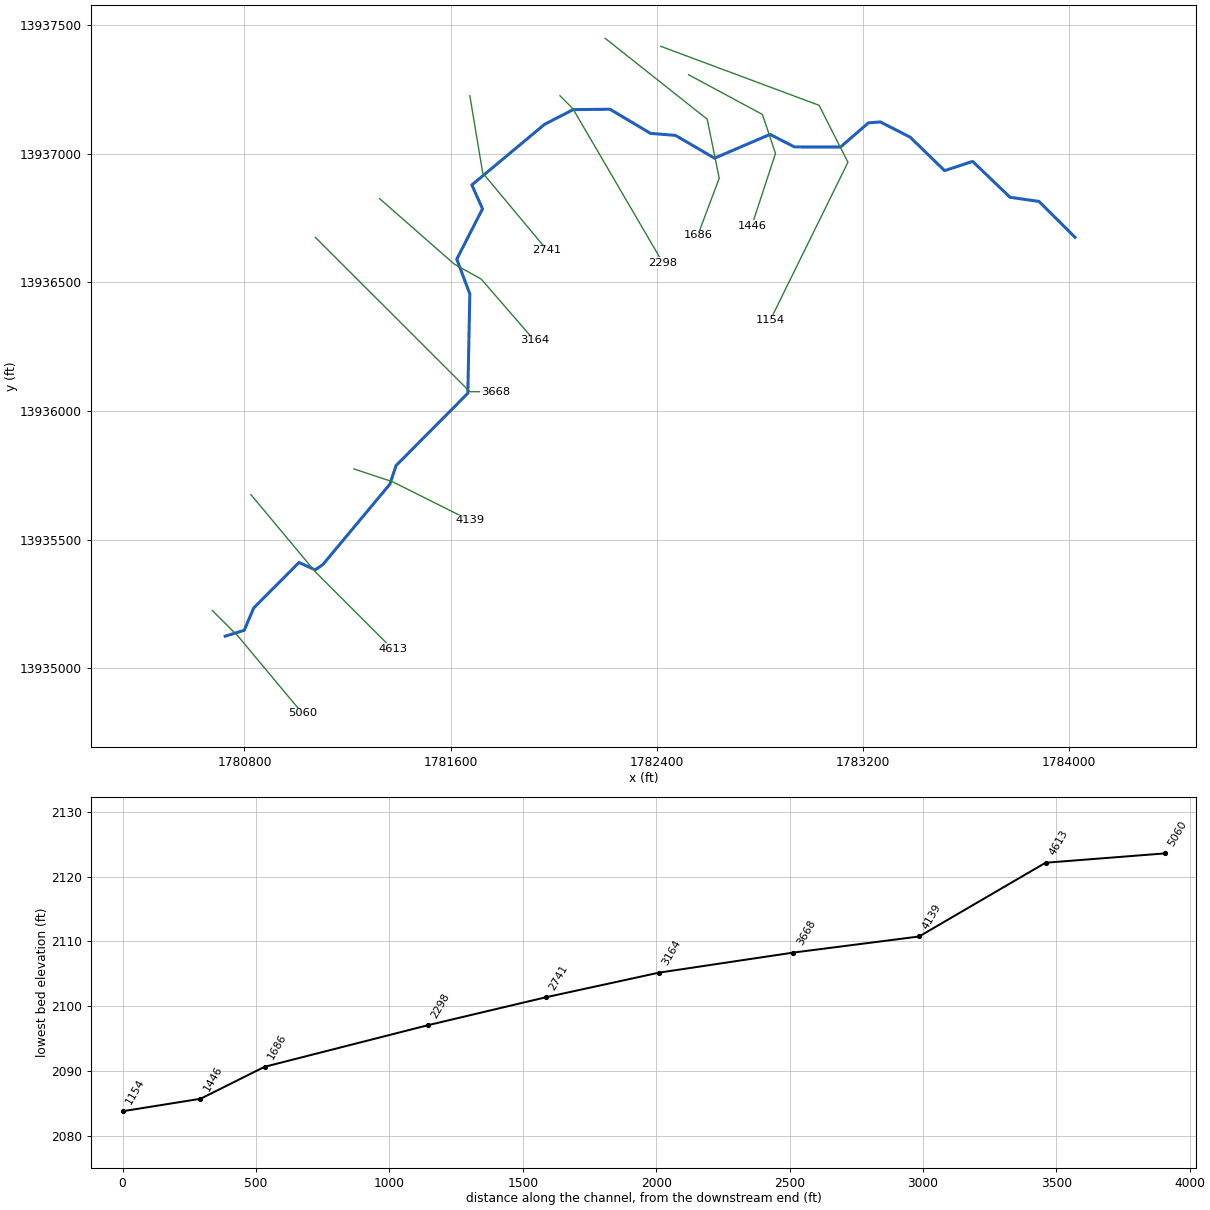
--- Stream0120.prj (project) ---

Proj Title=Stream0120 Base Level Engineering
Current Plan=p01
Default Exp/Contr=0.3,0.1
English Units
Geom File=g01
Flow File=f01
Plan File=p01
BEGIN DESCRIPTION:
Stream0120
END DESCRIPTION:

--- Stream0120.p01 (plan) ---

Plan Title=Multiple Run
Short Identifier=Multiple
Geom File=g01
Flow File=f01
Subcritical Flow
K Sum by GR= 0
Std Step Tol= 0.01
Critical Tol= 0.01
Num of Std Step Trials= 20
Max Error Tol= 0.3
Flow Tol Ratio= 0.001
Split Flow NTrial= 30
Split Flow Tol= 0.02
Split Flow Ratio= 0.02
Log Output Level= 0
Friction Slope Method= 1
Unsteady Friction Slope Method= 2
Unsteady Bridges Friction Slope Method= 1
Parabolic Critical Depth
Global Vel Dist=  1 , 1 , 1
Global Log Level= 0
CheckData=True
Encroach Param= -1, 0, 0, 0
BEGIN DESCRIPTION:
Multiple Run
END DESCRIPTION:

--- Stream0120.f01 (steady flow) ---

Flow Title=Multiple
Number of Profiles=7
Profile Names=10-year,25-year,50-year,1pct_min,100-year,1pct_plu,500-year
River Rch & RM= Stream0120,Reach-1,5060
    1093    1875    2620    1768    3529    7040    6330
Boundary for River Rch & Prof#=Stream0120,Reach-1,1
Up Type=0
Dn Type=3
Dn Slope=0.005
Boundary for River Rch & Prof#=Stream0120,Reach-1,2
Up Type=0
Dn Type=3
Dn Slope=0.005
Boundary for River Rch & Prof#=Stream0120,Reach-1,3
Up Type=0
Dn Type=3
Dn Slope=0.005
Boundary for River Rch & Prof#=Stream0120,Reach-1,4
Up Type=0
Dn Type=3
Dn Slope=0.005
Boundary for River Rch & Prof#=Stream0120,Reach-1,5
Up Type=0
Dn Type=3
Dn Slope=0.005
Boundary for River Rch & Prof#=Stream0120,Reach-1,6
Up Type=0
Dn Type=3
Dn Slope=0.005
Boundary for River Rch & Prof#=Stream0120,Reach-1,7
Up Type=0
Dn Type=3
Dn Slope=0.005

--- Stream0120.g01 (geometry) ---

Geom Title=Existing Conditions

River Reach=Stream0120,Reach-1
Reach XY= 30
      1780725.00     13935125.00      1780798.98     13935147.82
      1780835.77     13935234.67      1781011.67     13935411.35
      1781075.00     13935382.56      1781105.00     13935404.10
      1781364.22     13935715.32      1781388.63     13935788.21
      1781667.19     13936068.81      1781674.93     13936454.97
      1781624.28     13936590.06      1781724.20     13936785.70
      1781682.81     13936878.42      1781965.32     13937114.24
      1782076.56     13937171.26      1782219.07     13937172.77
      1782376.58     13937078.83      1782473.42     13937071.17
      1782624.99     13936982.53      1782840.39     13937074.91
      1782935.50     13937026.24      1783114.56     13937026.05
      1783222.71     13937119.90      1783268.88     13937123.24
      1783384.68     13937064.24      1783518.27     13936934.15
      1783627.29     13936969.88      1783772.57     13936830.52
      1783884.79     13936814.49      1784025.00     13936675.00

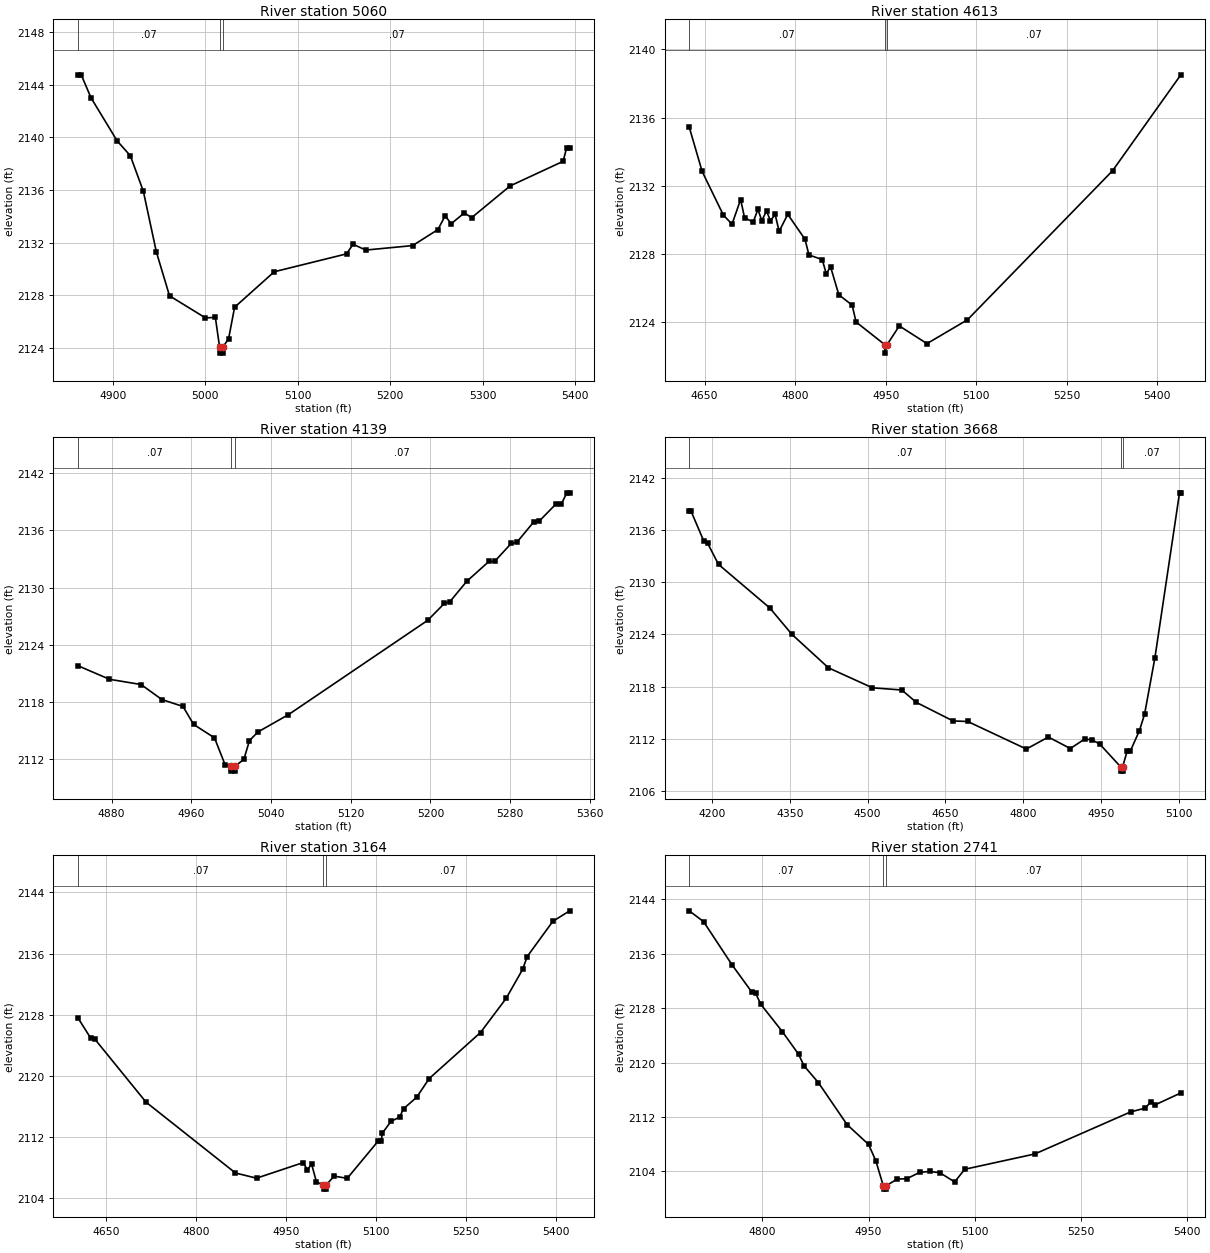
Type RM Length L Ch R = 1,5060,447,447,447
BEGIN DESCRIPTION:
Stream0120 7.0
END DESCRIPTION:
XS GIS Cut Line= 3
      1780675.01     13935224.99      1780775.00     13935125.00
      1781024.99     13934825.01
#Sta/Elev= 30
  4862.3 2144.76  4865.8 2144.76  4876.4 2143.01  4904.7 2139.73  4918.9 2138.61
  4933.0 2135.90  4947.1 2131.28  4961.3 2127.95  5000.2 2126.27  5010.9 2126.31
  5015.4 2124.09  5015.6 2123.59  5019.1 2123.59  5019.4 2124.09  5025.2 2124.68
  5031.7 2127.08  5074.6 2129.78  5152.8 2131.14  5159.9 2131.87  5173.6 2131.43
  5224.3 2131.77  5251.7 2132.99  5259.5 2134.04  5266.0 2133.43  5280.3 2134.26
  5288.1 2133.89  5329.8 2136.31  5387.1 2138.18  5391.0 2139.23  5394.2 2139.23
#Mann=3,-1,0
  4862.3    0.07       0  5015.4    0.05       0  5019.4    0.07       0
Bank Sta=5015.4,5019.4
Exp/Cntr=0.3,0.1

Type RM Length L Ch R = 1,4613,474,474,474
BEGIN DESCRIPTION:
Stream0120 6.0
END DESCRIPTION:
XS GIS Cut Line= 3
      1780824.99     13935675.01      1781075.00     13935375.00
      1781375.01     13935074.99
#Sta/Elev= 30
  4624.3 2135.45  4645.8 2132.83  4680.9 2130.27  4695.3 2129.73  4709.6 2131.18
  4716.1 2130.11  4730.4 2129.85  4738.2 2130.60  4744.7 2129.94  4752.5 2130.51
  4759.0 2129.93  4766.8 2130.30  4773.4 2129.31  4787.7 2130.31  4816.3 2128.84
  4822.8 2127.92  4844.9 2127.65  4851.5 2126.81  4858.6 2127.23  4872.3 2125.58
  4894.4 2124.97  4900.9 2123.98  4948.4 2122.65  4948.6 2122.15  4952.4 2122.65
  4972.5 2123.75  5018.4 2122.71  5085.5 2124.11  5325.9 2132.87  5439.1 2138.51
#Mann=3,-1,0
  4624.3    0.07       0  4948.4    0.05       0  4952.4    0.07       0
Bank Sta=4948.4,4952.4
Exp/Cntr=0.3,0.1

Type RM Length L Ch R = 1,4139,471,471,471
BEGIN DESCRIPTION:
Stream0120 5.0
END DESCRIPTION:
XS GIS Cut Line= 3
      1781224.98     13935775.01      1781375.00     13935725.00
      1781674.96     13935575.02
#Sta/Elev= 30
  4846.2 2121.82  4877.8 2120.40  4909.5 2119.85  4930.5 2118.27  4951.6 2117.55
  4962.2 2115.67  4983.2 2114.26  4993.8 2111.45  4999.7 2111.27  4999.9 2110.77
  5003.4 2110.77  5003.7 2111.27  5012.7 2112.01  5018.3 2113.97  5026.7 2114.87
  5057.4 2116.69  5197.2 2126.58  5214.0 2128.36  5219.6 2128.55  5236.3 2130.66
  5258.7 2132.76  5264.3 2132.75  5281.0 2134.64  5286.6 2134.75  5303.4 2136.87
  5309.0 2136.97  5325.8 2138.76  5331.4 2138.80  5336.9 2139.95  5339.7 2139.95
#Mann=3,-1,0
  4846.2    0.07       0  4999.7    0.05       0  5003.7    0.07       0
Bank Sta=4999.7,5003.7
Exp/Cntr=0.3,0.1

Type RM Length L Ch R = 1,3668,504,504,504
BEGIN DESCRIPTION:
Stream0120 4.0
END DESCRIPTION:
XS GIS Cut Line= 3
      1781074.98     13936675.02      1781675.00     13936075.00
      1781775.04     13936075.00
#Sta/Elev= 30
  4155.7 2138.19  4159.3 2138.19  4184.0 2134.73  4191.1 2134.52  4212.3 2132.06
  4311.3 2127.05  4353.7 2124.03  4424.4 2120.17  4509.3 2117.87  4565.9 2117.62
  4594.1 2116.19  4664.9 2114.06  4693.1 2114.00  4806.3 2110.83  4848.7 2112.21
  4891.1 2110.89  4919.4 2112.00  4933.6 2111.86  4947.7 2111.41  4988.1 2108.79
  4988.4 2108.29  4991.9 2108.29  4992.1 2108.79  5000.7 2110.59  5006.8 2110.59
  5024.3 2112.93  5034.3 2114.82  5054.3 2121.33  5101.8 2140.29  5104.3 2140.29
#Mann=3,-1,0
  4155.7    0.07       0  4988.1    0.05       0  4992.1    0.07       0
Bank Sta=4988.1,4992.1
Exp/Cntr=0.3,0.1

Type RM Length L Ch R = 1,3164,423,423,423
BEGIN DESCRIPTION:
Stream0120 3.0
END DESCRIPTION:
XS GIS Cut Line= 4
      1781325.00     13936825.00      1781614.90     13936570.58
      1781719.25     13936512.62      1781925.01     13936274.99
#Sta/Elev= 30
  4603.6 2127.57  4624.9 2124.92  4631.6 2124.81  4717.0 2116.56  4866.0 2107.30
  4901.1 2106.62  4978.9 2108.66  4986.0 2107.67  4992.8 2108.49  5000.9 2106.16
  5012.6 2105.69  5012.8 2105.19  5016.3 2105.19  5016.6 2105.69  5030.6 2106.89
  5052.3 2106.60  5103.4 2111.43  5108.7 2111.43  5111.0 2112.53  5125.2 2114.05
  5139.5 2114.60  5146.1 2115.70  5168.0 2117.20  5188.9 2119.65  5274.4 2125.67
  5317.1 2130.13  5344.6 2133.92  5352.2 2135.60  5395.0 2140.21  5423.0 2141.58
#Mann=3,-1,0
  4603.6    0.07       0  5012.6    0.05       0  5016.6    0.07       0
Bank Sta=5012.6,5016.6
Exp/Cntr=0.3,0.1

Type RM Length L Ch R = 1,2741,443,443,443
BEGIN DESCRIPTION:
Stream0120 2.0
END DESCRIPTION:
XS GIS Cut Line= 3
      1781674.99     13937225.04      1781725.00     13936925.00
      1781975.00     13936624.99
#Sta/Elev= 30
  4696.5 2142.32  4716.8 2140.74  4757.4 2134.33  4785.2 2130.35  4790.3 2130.22
  4797.9 2128.55  4828.3 2124.54  4851.1 2121.23  4858.7 2119.54  4879.0 2117.07
  4919.6 2110.89  4950.0 2107.97  4960.1 2105.60  4970.8 2101.90  4971.1 2101.40
  4974.6 2101.40  4974.8 2101.90  4990.5 2102.88  5003.9 2102.93  5022.2 2103.86
  5036.5 2104.01  5050.8 2103.81  5071.6 2102.46  5085.9 2104.32  5184.9 2106.57
  5320.2 2112.75  5341.1 2113.32  5348.9 2114.26  5355.4 2113.82  5391.2 2115.54
#Mann=3,-1,0
  4696.5    0.07       0  4970.8    0.05       0  4974.8    0.07       0
Bank Sta=4970.8,4974.8
Exp/Cntr=0.3,0.1

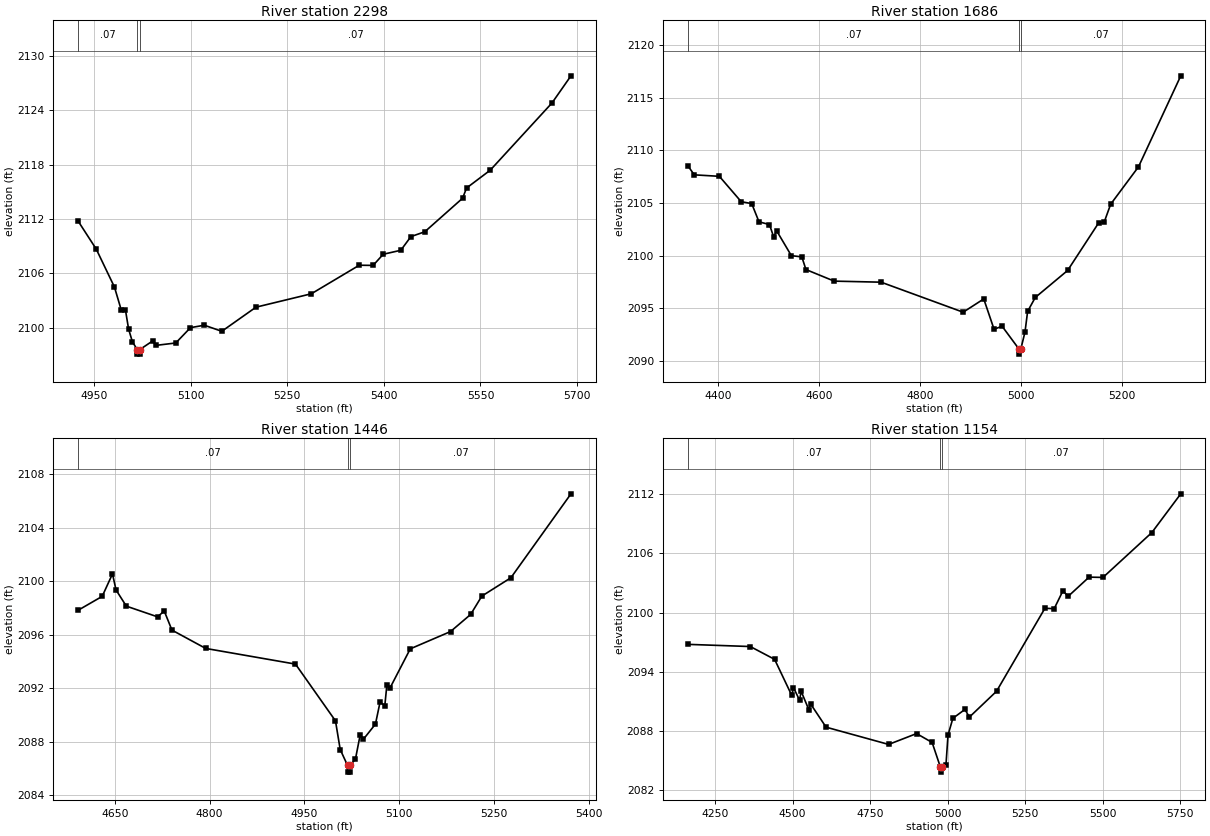
Type RM Length L Ch R = 1,2298,612,612,612
BEGIN DESCRIPTION:
Stream0120 1.0
END DESCRIPTION:
XS GIS Cut Line= 3
      1782025.02     13937224.98      1782075.00     13937175.00
      1782425.00     13936575.00
#Sta/Elev= 30
  4925.2 2111.77  4953.5 2108.66  4981.7 2104.48  4992.3 2101.94  4998.8 2101.94
  5003.7 2099.83  5009.5 2098.46  5017.0 2097.58  5017.3 2097.08  5020.8 2097.08
  5021.0 2097.58  5040.9 2098.53  5046.7 2098.05  5076.9 2098.31  5099.7 2100.00
  5121.2 2100.27  5148.4 2099.60  5201.4 2102.26  5287.4 2103.74  5361.8 2106.89
  5383.3 2106.87  5399.0 2108.10  5426.3 2108.54  5442.0 2110.05  5463.5 2110.58
  5522.2 2114.28  5528.4 2115.41  5565.2 2117.38  5661.1 2124.80  5690.5 2127.79
#Mann=3,-1,0
  4925.2    0.07       0  5017.0    0.05       0  5021.0    0.07       0
Bank Sta=5017,5021
Exp/Cntr=0.3,0.1

Type RM Length L Ch R = 1,1686,240,240,240
BEGIN DESCRIPTION:
Stream0120 0.1
END DESCRIPTION:
XS GIS Cut Line= 4
      1782200.45     13937448.24      1782596.57     13937133.93
      1782643.31     13936904.43      1782559.98     13936682.97
#Sta/Elev= 30
  4340.2 2108.54  4352.9 2107.68  4402.6 2107.54  4445.9 2105.13  4466.7 2104.95
  4481.1 2103.22  4501.9 2102.96  4510.0 2101.81  4516.3 2102.35  4545.2 2100.01
  4566.0 2099.89  4574.1 2098.69  4630.1 2097.59  4723.0 2097.49  4885.6 2094.64
  4926.4 2095.90  4946.8 2093.02  4962.7 2093.31  4995.9 2091.16  4996.1 2090.66
  4999.9 2091.16  5008.1 2092.76  5013.3 2094.72  5028.5 2096.04  5092.5 2098.60
  5154.3 2103.14  5164.9 2103.18  5177.8 2104.89  5232.9 2108.44  5316.7 2117.08
#Mann=3,-1,0
  4340.2    0.07       0  4995.9    0.05       0  4999.9    0.07       0
Bank Sta=4995.9,4999.9
Exp/Cntr=0.3,0.1

Type RM Length L Ch R = 1,1446,292,292,292
BEGIN DESCRIPTION:
Stream0120 0.0
END DESCRIPTION:
XS GIS Cut Line= 4
      1782524.13     13937306.93      1782811.04     13937152.41
      1782861.70     13937000.96      1782769.99     13936720.87
#Sta/Elev= 30
  4591.9 2097.82  4630.1 2098.86  4646.4 2100.54  4652.0 2099.34  4668.3 2098.13
  4717.8 2097.33  4728.3 2097.77  4740.5 2096.34  4794.0 2094.97  4936.1 2093.80
  4999.4 2089.56  5006.9 2087.42  5018.5 2086.23  5018.7 2085.73  5022.2 2085.73
  5022.5 2086.23  5031.0 2086.70  5038.5 2088.51  5043.7 2088.19  5062.7 2089.32
  5070.0 2090.97  5077.5 2090.69  5080.7 2092.21  5086.0 2092.04  5117.8 2094.94
  5181.5 2096.23  5213.4 2097.51  5231.1 2098.88  5277.1 2100.25  5372.2 2106.52
#Mann=3,-1,0
  4591.9    0.07       0  5018.5    0.05       0  5022.5    0.07       0
Bank Sta=5018.5,5022.5
Exp/Cntr=0.3,0.1

Type RM Length L Ch R = 1,1154,0,0,0
BEGIN DESCRIPTION:
Stream0120 0.2
END DESCRIPTION:
XS GIS Cut Line= 4
      1782416.46     13937417.13      1783031.03     13937187.96
      1783143.01     13936966.61      1782840.92     13936352.02
#Sta/Elev= 30
  4162.4 2096.77  4363.6 2096.55  4442.0 2095.25  4497.3 2091.59  4502.7 2092.39
  4522.3 2091.12  4527.7 2092.00  4552.6 2090.12  4558.0 2090.73  4607.9 2088.37
  4809.5 2086.62  4899.6 2087.72  4949.7 2086.82  4976.5 2084.31  4976.8 2083.81
  4980.5 2084.31  4994.3 2084.51  5000.9 2087.56  5016.6 2089.27  5055.5 2090.17
  5069.8 2089.39  5157.3 2092.01  5313.3 2100.43  5343.2 2100.39  5371.3 2102.20
  5388.2 2101.64  5455.6 2103.59  5500.5 2103.56  5657.9 2108.11  5751.2 2112.04
#Mann=3,-1,0
  4162.4    0.07       0  4976.5    0.05       0  4980.5    0.07       0
Bank Sta=4976.5,4980.5
Exp/Cntr=0.3,0.1

Chan Stop Cuts=-1