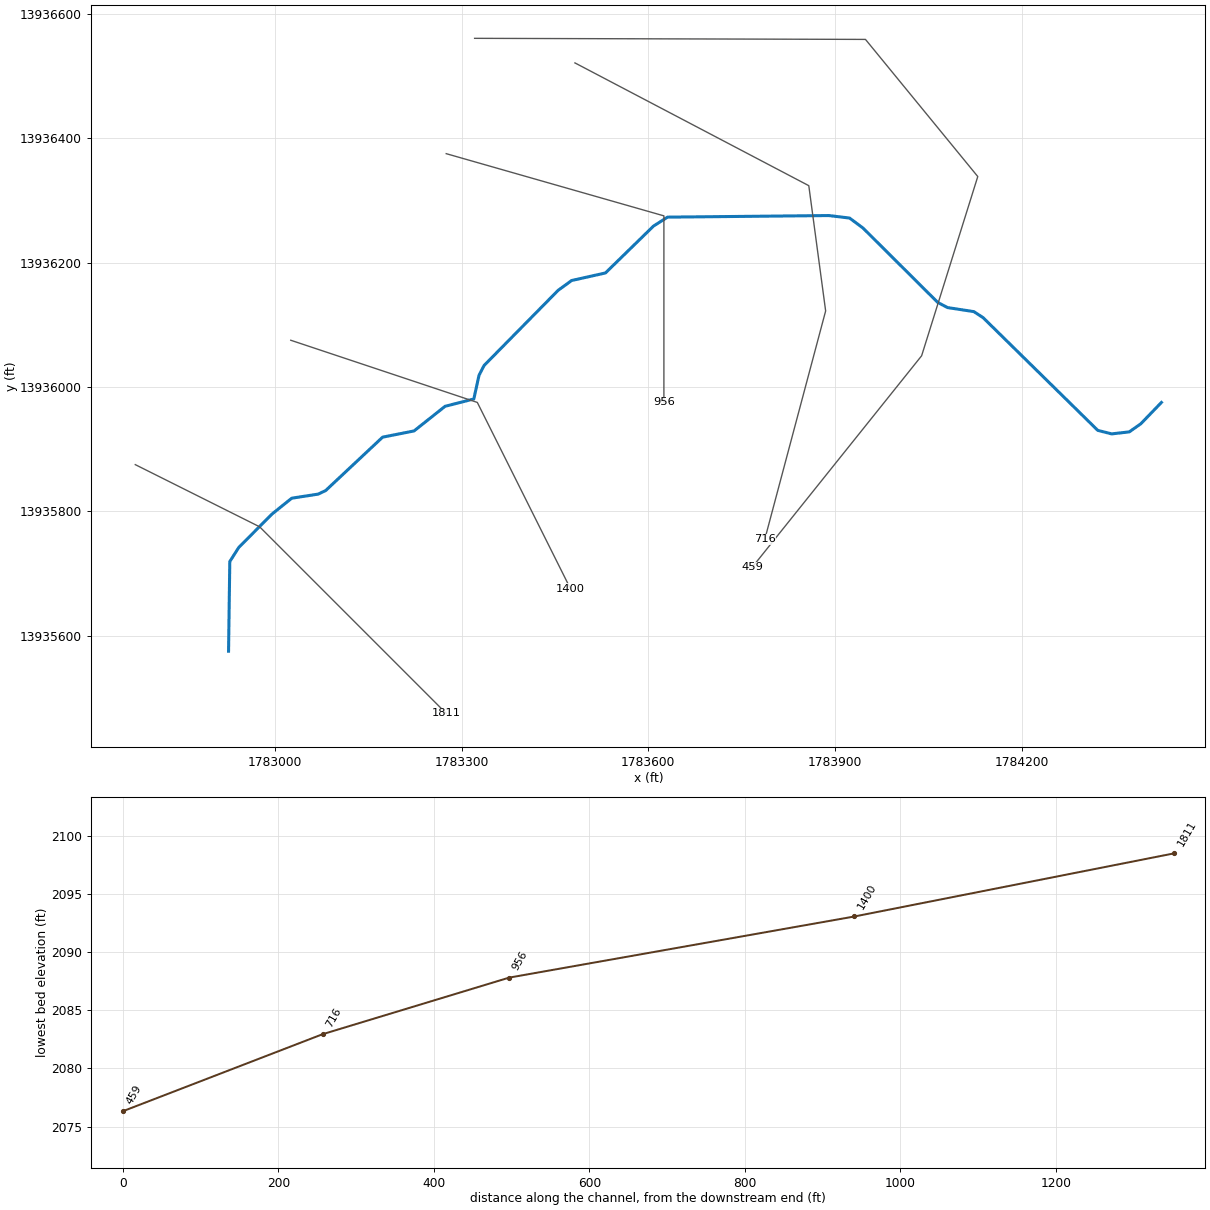
--- Stream0121.prj (project) ---

Proj Title=Stream0121 Base Level Engineering
Current Plan=p01
Default Exp/Contr=0.3,0.1
English Units
Geom File=g01
Flow File=f01
Plan File=p01
BEGIN DESCRIPTION:
Stream0121
END DESCRIPTION:

--- Stream0121.p01 (plan) ---

Plan Title=Multiple Run
Short Identifier=Multiple
Geom File=g01
Flow File=f01
Subcritical Flow
K Sum by GR= 0
Std Step Tol= 0.01
Critical Tol= 0.01
Num of Std Step Trials= 20
Max Error Tol= 0.3
Flow Tol Ratio= 0.001
Split Flow NTrial= 30
Split Flow Tol= 0.02
Split Flow Ratio= 0.02
Log Output Level= 0
Friction Slope Method= 1
Unsteady Friction Slope Method= 2
Unsteady Bridges Friction Slope Method= 1
Parabolic Critical Depth
Global Vel Dist=  1 , 1 , 1
Global Log Level= 0
CheckData=True
Encroach Param= -1, 0, 0, 0
BEGIN DESCRIPTION:
Multiple Run
END DESCRIPTION:

--- Stream0121.f01 (steady flow) ---

Flow Title=Multiple
Number of Profiles=7
Profile Names=10-year,25-year,50-year,1pct_min,100-year,1pct_plu,500-year
River Rch & RM= Stream0121,Reach-1,1811
     477     778    1052     690    1377    2748    2326
Boundary for River Rch & Prof#=Stream0121,Reach-1,1
Up Type=0
Dn Type=3
Dn Slope=0.005
Boundary for River Rch & Prof#=Stream0121,Reach-1,2
Up Type=0
Dn Type=3
Dn Slope=0.005
Boundary for River Rch & Prof#=Stream0121,Reach-1,3
Up Type=0
Dn Type=3
Dn Slope=0.005
Boundary for River Rch & Prof#=Stream0121,Reach-1,4
Up Type=0
Dn Type=3
Dn Slope=0.005
Boundary for River Rch & Prof#=Stream0121,Reach-1,5
Up Type=0
Dn Type=3
Dn Slope=0.005
Boundary for River Rch & Prof#=Stream0121,Reach-1,6
Up Type=0
Dn Type=3
Dn Slope=0.005
Boundary for River Rch & Prof#=Stream0121,Reach-1,7
Up Type=0
Dn Type=3
Dn Slope=0.005

--- Stream0121.g01 (geometry) ---

Geom Title=Existing Conditions

River Reach=Stream0121,Reach-1
Reach XY= 30
      1782925.00     13935575.00      1782927.00     13935719.18
      1782941.41     13935741.80      1782994.76     13935795.42
      1783026.63     13935821.03      1783068.95     13935827.54
      1783081.04     13935833.18      1783172.71     13935919.15
      1783223.29     13935929.18      1783273.15     13935968.76
      1783319.39     13935980.59      1783327.69     13936018.57
      1783335.89     13936034.42      1783454.91     13936155.21
      1783476.65     13936171.03      1783531.04     13936183.18
      1783608.25     13936258.54      1783630.86     13936272.94
      1783890.20     13936275.49      1783923.54     13936271.46
      1783945.16     13936255.39      1784065.32     13936135.78
      1784081.05     13936127.54      1784123.35     13936121.02
      1784138.21     13936111.37      1784322.66     13935930.06
      1784345.06     13935924.42      1784373.38     13935927.67
      1784391.92     13935940.74      1784425.00     13935975.00

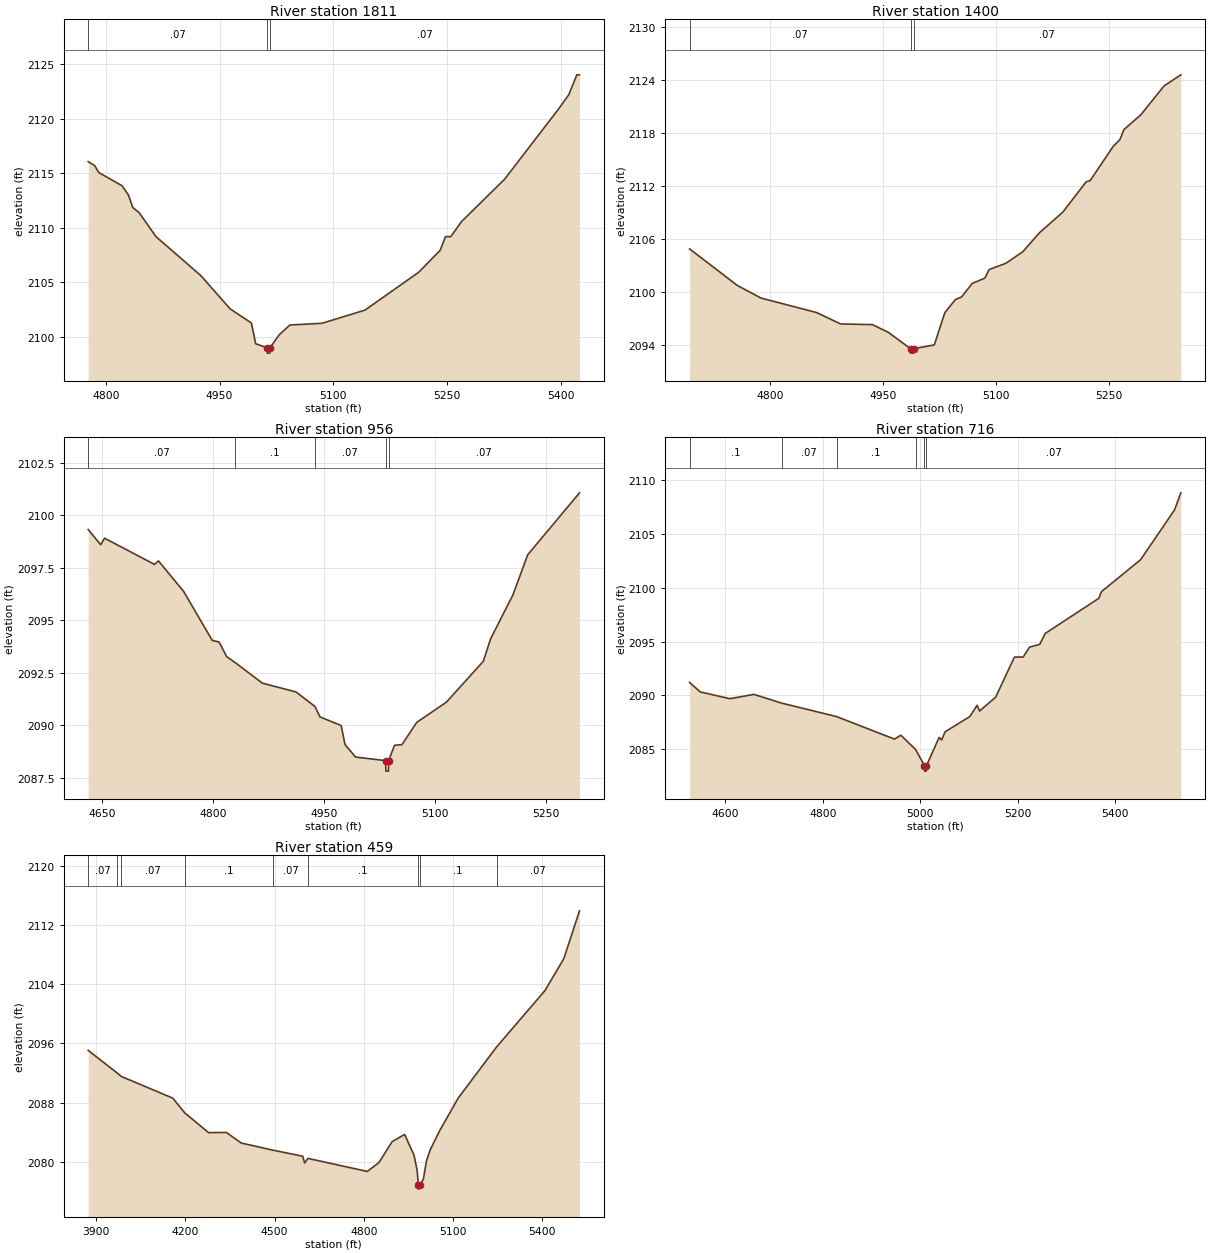
Type RM Length L Ch R = 1,1811,411,411,411
BEGIN DESCRIPTION:
Stream0121 3.0
END DESCRIPTION:
XS GIS Cut Line= 3
      1782775.02     13935874.99      1782975.00     13935775.00
      1783274.97     13935475.03
#Sta/Elev= 30
  4776.9 2116.08  4785.3 2115.73  4790.9 2115.08  4821.6 2113.87  4830.0 2113.01
  4835.6 2111.88  4844.0 2111.40  4866.3 2109.20  4925.0 2105.65  4964.1 2102.57
  4992.1 2101.27  4997.7 2099.37  5012.6 2099.01  5012.9 2098.51  5016.4 2098.51
  5016.6 2099.01  5028.8 2100.20  5042.9 2101.09  5085.3 2101.25  5141.9 2102.46
  5212.6 2105.93  5240.9 2107.94  5248.0 2109.20  5255.0 2109.20  5269.2 2110.59
  5325.8 2114.46  5396.5 2120.86  5410.6 2122.23  5421.2 2124.05  5424.7 2124.05
#Mann=3,-1,0
  4776.9    0.07       0  5012.6    0.05       0  5016.6    0.07       0
Bank Sta=5012.6,5016.6
Exp/Cntr=0.3,0.1

Type RM Length L Ch R = 1,1400,444,444,444
BEGIN DESCRIPTION:
Stream0121 2.0
END DESCRIPTION:
XS GIS Cut Line= 3
      1783025.01     13936075.00      1783325.00     13935975.00
      1783474.99     13935675.03
#Sta/Elev= 30
  4693.7 2104.88  4756.9 2100.75  4788.6 2099.31  4862.3 2097.67  4894.0 2096.38
  4936.1 2096.31  4957.2 2095.44  4986.8 2093.58  4987.1 2093.08  4990.6 2093.08
  4990.8 2093.58  5018.3 2094.01  5032.3 2097.67  5046.3 2099.14  5054.6 2099.45
  5068.6 2100.97  5085.4 2101.57  5091.0 2102.54  5113.3 2103.25  5135.7 2104.56
  5158.1 2106.73  5188.8 2109.04  5219.6 2112.46  5225.1 2112.62  5255.9 2116.52
  5264.3 2117.22  5269.9 2118.39  5292.2 2120.05  5323.0 2123.32  5345.3 2124.58
#Mann=3,-1,0
  4693.7    0.07       0  4986.8    0.05       0  4990.8    0.07       0
Bank Sta=4986.8,4990.8
Exp/Cntr=0.3,0.1

Type RM Length L Ch R = 1,956,240,240,240
BEGIN DESCRIPTION:
Stream0121 1.0
END DESCRIPTION:
XS GIS Cut Line= 3
      1783274.98     13936375.01      1783625.00     13936275.00
      1783625.00     13935975.03
#Sta/Elev= 30
  4631.7 2099.32  4648.6 2098.60  4653.8 2098.91  4721.4 2097.66  4726.6 2097.83
  4760.4 2096.39  4799.4 2094.04  4808.5 2093.97  4818.9 2093.27  4830.6 2092.98
  4867.0 2092.01  4912.5 2091.59  4938.1 2090.90  4945.0 2090.40  4973.6 2089.99
  4978.8 2089.08  4993.1 2088.49  5033.7 2088.32  5034.0 2087.82  5037.5 2087.82
  5037.7 2088.32  5045.7 2089.05  5055.7 2089.08  5075.7 2090.14  5115.7 2091.10
  5165.7 2093.05  5175.7 2094.13  5205.7 2096.21  5225.7 2098.12  5295.7 2101.07
#Mann=5,-1,0
  4631.7    0.07       0  4830.6     0.1       0  4938.1    0.07       0
  5033.7    0.05       0  5037.7    0.07       0
Bank Sta=5033.7,5037.7
Exp/Cntr=0.3,0.1

Type RM Length L Ch R = 1,716,257,257,257
BEGIN DESCRIPTION:
Stream0121 0.0
END DESCRIPTION:
XS GIS Cut Line= 4
      1783481.96     13936520.94      1783857.99     13936323.53
      1783885.08     13936122.10      1783787.32     13935755.24
#Sta/Elev= 30
  4526.7 2091.20  4548.6 2090.32  4609.2 2089.69  4658.9 2090.09  4715.3 2089.28
  4828.6 2088.02  4946.9 2085.93  4960.0 2086.29  4990.4 2084.96  5008.5 2083.45
  5008.7 2082.95  5012.2 2082.95  5012.5 2083.45  5038.6 2086.09  5043.6 2085.84
  5050.8 2086.61  5101.3 2088.02  5116.5 2089.07  5121.5 2088.54  5154.6 2089.84
  5193.0 2093.56  5210.9 2093.56  5224.1 2094.49  5244.8 2094.74  5256.2 2095.76
  5366.2 2099.03  5371.3 2099.64  5451.8 2102.62  5521.5 2107.26  5534.3 2108.84
#Mann=6,-1,0
  4526.7     0.1       0  4715.3    0.07       0  4828.6     0.1       0
  4990.4    0.07       0  5008.5    0.05       0  5012.5    0.07       0
Bank Sta=5008.5,5012.5
Exp/Cntr=0.3,0.1

Type RM Length L Ch R = 1,459,0,0,0
BEGIN DESCRIPTION:
Stream0121 6.0
END DESCRIPTION:
XS GIS Cut Line= 5
      1783320.64     13936560.44      1783949.13     13936558.71
      1784129.69     13936338.22      1784039.41     13936050.02
      1783766.94     13935709.87
#Sta/Elev= 30
  3873.8 2095.05  3969.0 2092.06  3984.7 2091.54  4158.2 2088.60  4198.0 2086.62
  4278.2 2083.95  4338.2 2083.97  4388.2 2082.54  4493.8 2081.59  4594.7 2080.76
  4601.2 2079.85  4612.3 2080.47  4811.6 2078.71  4850.7 2079.89  4895.4 2082.74
  4937.4 2083.70  4968.8 2080.91  4979.3 2078.87  4983.7 2076.82  4984.0 2076.32
  4987.7 2076.82  5000.2 2077.65  5010.7 2080.13  5023.4 2081.64  5055.9 2084.27
  5117.6 2088.63  5246.8 2095.53  5408.9 2103.12  5472.2 2107.42  5525.1 2113.89
#Mann=9,-1,0
  3873.8    0.07       0  3969.0     0.1       0  3984.7    0.07       0
  4198.0     0.1       0  4493.8    0.07       0  4612.3     0.1       0
  4983.7    0.05       0  4987.7     0.1       0  5246.8    0.07       0
Bank Sta=4983.7,4987.7
Exp/Cntr=0.3,0.1

Chan Stop Cuts=-1