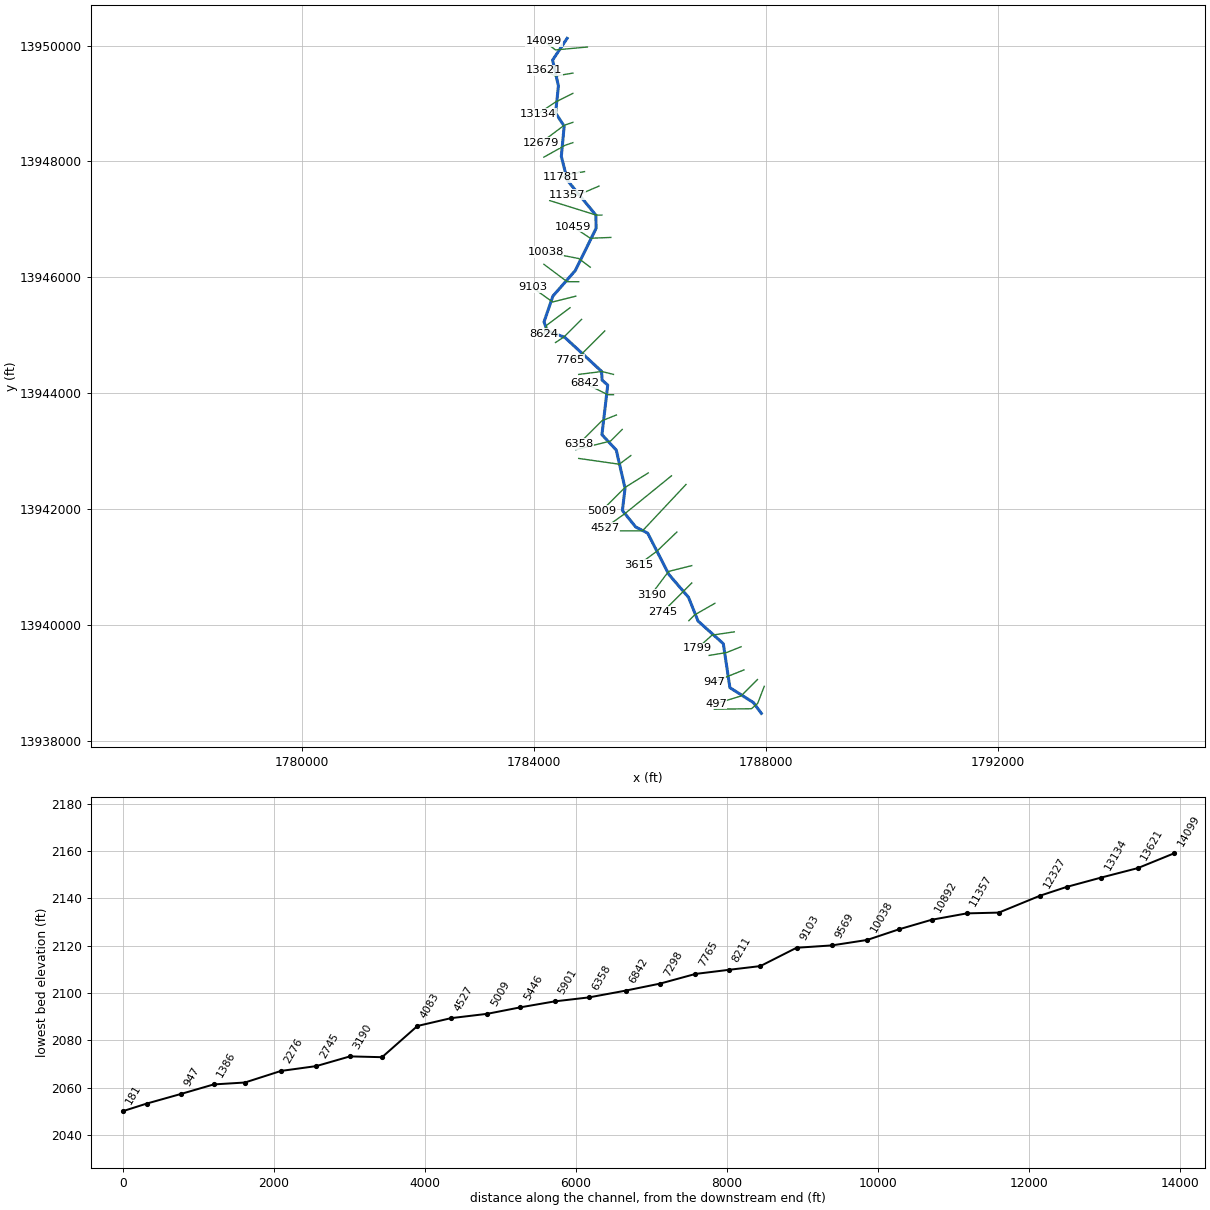
--- Stream0123.prj (project) ---

Proj Title=Stream0123 Base Level Engineering
Current Plan=p01
Default Exp/Contr=0.3,0.1
English Units
Geom File=g01
Flow File=f01
Plan File=p01
BEGIN DESCRIPTION:
Stream0123
END DESCRIPTION:

--- Stream0123.p01 (plan) ---

Plan Title=Multiple Run
Short Identifier=Multiple
Geom File=g01
Flow File=f01
Subcritical Flow
K Sum by GR= 0
Std Step Tol= 0.01
Critical Tol= 0.01
Num of Std Step Trials= 20
Max Error Tol= 0.3
Flow Tol Ratio= 0.001
Split Flow NTrial= 30
Split Flow Tol= 0.02
Split Flow Ratio= 0.02
Log Output Level= 0
Friction Slope Method= 1
Unsteady Friction Slope Method= 2
Unsteady Bridges Friction Slope Method= 1
Parabolic Critical Depth
Global Vel Dist=  1 , 1 , 1
Global Log Level= 0
CheckData=True
Encroach Param= -1, 0, 0, 0
BEGIN DESCRIPTION:
Multiple Run
END DESCRIPTION:

--- Stream0123.f01 (steady flow) ---

Flow Title=Multiple
Number of Profiles=7
Profile Names=10-year,25-year,50-year,1pct_min,100-year,1pct_plu,500-year
River Rch & RM= Stream0123,Reach-1,14099
    1953    3450    4916    3376    6736   13441   12520
River Rch & RM= Stream0123,Reach-1,11781
    2229    3955    5653    3890    7762   15488   14496
River Rch & RM= Stream0123,Reach-1,8624
    2637    4709    6759    4668    9315   18586   17522
River Rch & RM= Stream0123,Reach-1,5446
    2884    5170    7439    5150   10276   20503   19418
River Rch & RM= Stream0123,Reach-1,3190
    3094    5558    8008    5549   11072   22092   20967
Boundary for River Rch & Prof#=Stream0123,Reach-1,1
Up Type=0
Dn Type=3
Dn Slope=0.005
Boundary for River Rch & Prof#=Stream0123,Reach-1,2
Up Type=0
Dn Type=3
Dn Slope=0.005
Boundary for River Rch & Prof#=Stream0123,Reach-1,3
Up Type=0
Dn Type=3
Dn Slope=0.005
Boundary for River Rch & Prof#=Stream0123,Reach-1,4
Up Type=0
Dn Type=3
Dn Slope=0.005
Boundary for River Rch & Prof#=Stream0123,Reach-1,5
Up Type=0
Dn Type=3
Dn Slope=0.005
Boundary for River Rch & Prof#=Stream0123,Reach-1,6
Up Type=0
Dn Type=3
Dn Slope=0.005
Boundary for River Rch & Prof#=Stream0123,Reach-1,7
Up Type=0
Dn Type=3
Dn Slope=0.005

--- Stream0123.g01 (geometry) ---

Geom Title=Existing Conditions

River Reach=Stream0123,Reach-1
Reach XY= 30
      1784575.00     13950125.00      1784324.80     13949750.08
      1784425.28     13949304.82      1784376.20     13948835.50
      1784524.61     13948609.84      1784475.38     13948090.27
      1784580.54     13947672.58      1785071.46     13947073.54
      1785074.94     13946845.03      1784717.14     13946118.83
      1784330.47     13945677.45      1784176.98     13945231.27
      1784230.10     13945080.10      1784535.00     13944964.37
      1785169.53     13944377.45      1785178.49     13944226.27
      1785275.63     13944140.55      1785175.64     13943285.63
      1785422.76     13943019.07      1785574.48     13942359.78
      1785528.47     13941976.50      1785758.32     13941691.64
      1785964.61     13941585.11      1786330.35     13940872.50
      1786669.16     13940477.29      1786833.14     13940068.94
      1787269.17     13939677.30      1787382.81     13938918.81
      1787788.22     13938661.38      1787925.00     13938475.00

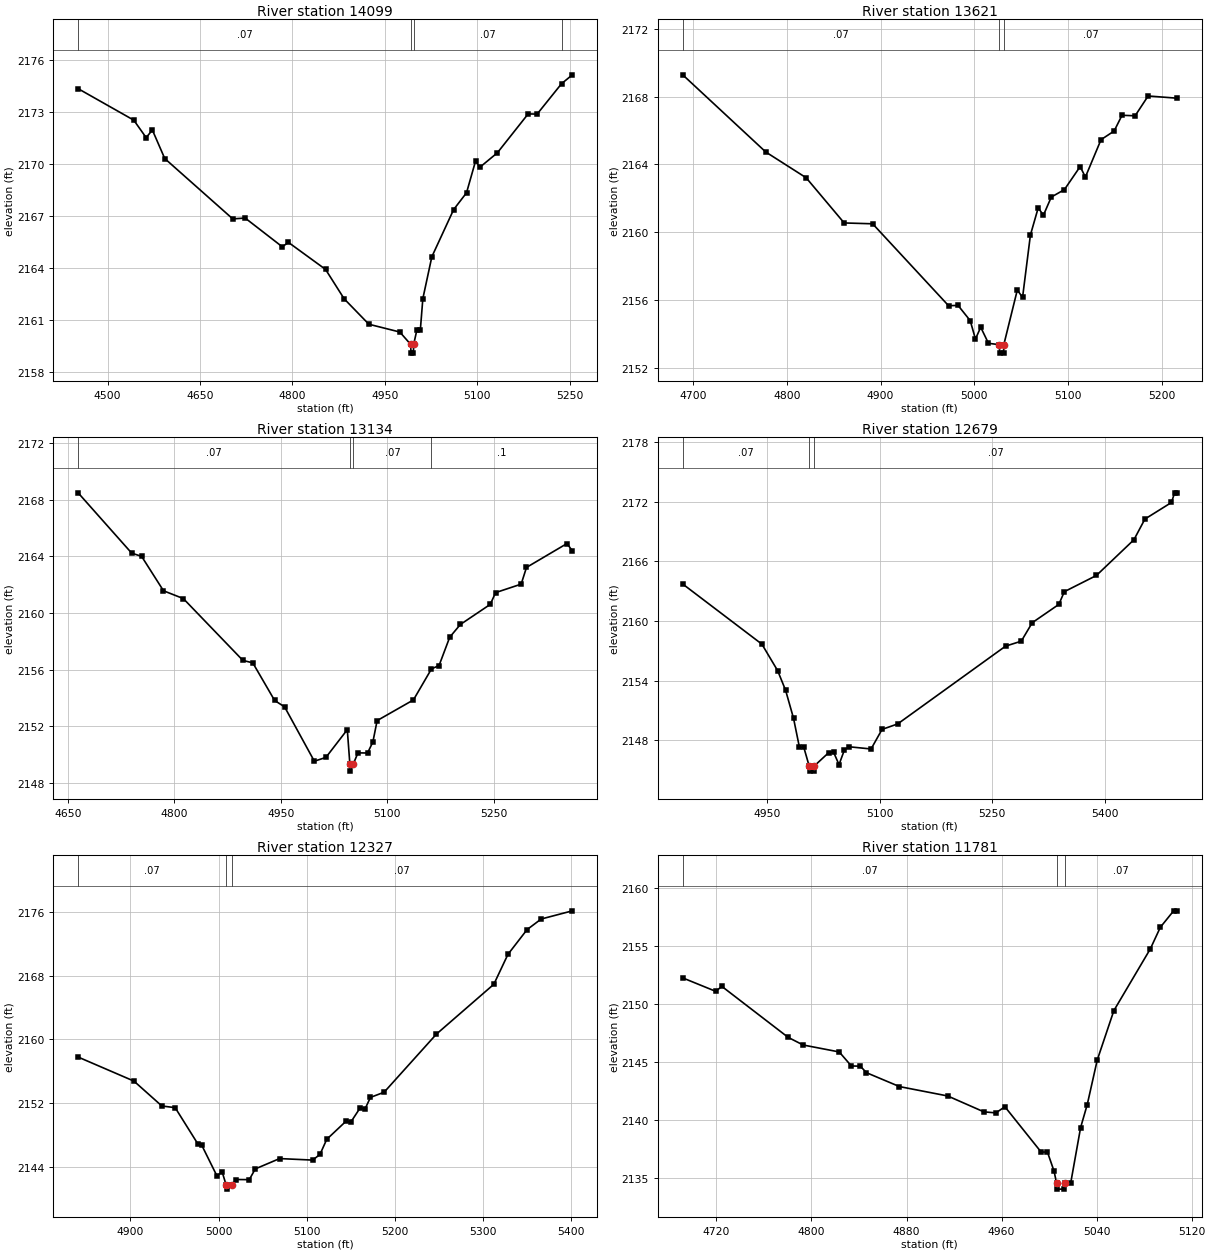
Type RM Length L Ch R = 1,14099,478,478,478
BEGIN DESCRIPTION:
Stream0123 31.0
END DESCRIPTION:
XS GIS Cut Line= 3
      1784924.98     13949975.00      1784375.00     13949925.00
      1784175.04     13950074.97
#Sta/Elev= 30
  4452.1 2174.36  4542.4 2172.54  4562.5 2171.53  4572.6 2171.97  4592.7 2170.32
  4703.1 2166.83  4723.2 2166.88  4783.4 2165.22  4793.5 2165.47  4853.7 2163.91
  4883.9 2162.21  4924.0 2160.74  4974.2 2160.29  4992.0 2159.57  4992.3 2159.07
  4996.3 2159.07  4996.7 2159.57  5001.8 2160.39  5007.5 2160.39  5011.6 2162.22
  5026.2 2164.64  5061.6 2167.37  5082.5 2168.34  5097.1 2170.17  5104.3 2169.82
  5132.5 2170.65  5182.5 2172.90  5197.1 2172.89  5236.8 2174.65  5254.3 2175.16
#Mann=4,-1,0
  4452.1    0.07       0  4992.0    0.05       0  4996.7    0.07       0
  5236.8     0.1       0
Bank Sta=4992,4996.7
Exp/Cntr=0.3,0.1

Type RM Length L Ch R = 1,13621,487,487,487
BEGIN DESCRIPTION:
Stream0123 30.0
END DESCRIPTION:
XS GIS Cut Line= 3
      1784675.04     13949525.01      1784375.00     13949475.00
      1784174.99     13949575.01
#Sta/Elev= 30
  4688.7 2169.29  4777.4 2164.73  4820.5 2163.21  4861.1 2160.54  4891.5 2160.49
  4972.6 2155.65  4982.7 2155.67  4995.7 2154.77  5001.3 2153.68  5006.9 2154.38
  5015.2 2153.43  5026.8 2153.35  5027.2 2152.85  5031.3 2152.85  5031.6 2153.35
  5046.0 2156.58  5051.6 2156.14  5060.0 2159.83  5068.3 2161.43  5073.9 2161.00
  5082.3 2162.07  5096.3 2162.51  5113.1 2163.87  5118.7 2163.25  5135.4 2165.46
  5149.4 2165.97  5157.8 2166.90  5171.8 2166.87  5185.7 2168.04  5216.5 2167.91
#Mann=3,-1,0
  4688.7    0.07       0  5026.8    0.05       0  5031.6    0.07       0
Bank Sta=5026.8,5031.6
Exp/Cntr=0.3,0.1

Type RM Length L Ch R = 1,13134,455,455,455
BEGIN DESCRIPTION:
Stream0123 29.0
END DESCRIPTION:
XS GIS Cut Line= 3
      1784674.98     13949174.99      1784375.00     13949025.00
      1784075.04     13948825.03
#Sta/Elev= 30
  4664.6 2168.49  4740.0 2164.23  4754.0 2164.00  4784.8 2161.57  4812.7 2161.02
  4896.6 2156.65  4910.5 2156.48  4941.3 2153.82  4955.3 2153.37  4997.2 2149.53
  5013.5 2149.80  5043.6 2151.76  5047.2 2149.33  5047.5 2148.83  5052.0 2149.33
  5058.6 2150.12  5072.1 2150.11  5079.6 2150.89  5085.6 2152.40  5136.7 2153.86
  5162.1 2156.05  5172.8 2156.29  5187.8 2158.29  5202.8 2159.19  5244.9 2160.61
  5252.4 2161.44  5288.4 2162.04  5295.9 2163.22  5353.0 2164.91  5360.5 2164.38
#Mann=4,-1,0
  4664.6    0.07       0  5047.2    0.05       0  5052.0    0.07       0
  5162.1     0.1       0
Bank Sta=5047.2,5052
Exp/Cntr=0.3,0.1

Type RM Length L Ch R = 1,12679,352,352,352
BEGIN DESCRIPTION:
Stream0123 28.0
END DESCRIPTION:
XS GIS Cut Line= 3
      1784674.96     13948674.99      1784525.00     13948625.00
      1784124.97     13948324.98
#Sta/Elev= 30
  4837.9 2163.72  4943.3 2157.67  4964.3 2155.00  4974.9 2153.02  4985.4 2150.22
  4993.3 2147.29  4999.1 2147.29  5006.3 2145.39  5006.8 2144.89  5012.3 2144.89
  5012.8 2145.39  5032.4 2146.76  5038.7 2146.81  5046.0 2145.54  5053.3 2147.05
  5059.5 2147.34  5088.7 2147.12  5103.3 2149.09  5124.1 2149.64  5267.8 2157.47
  5288.7 2157.97  5303.3 2159.83  5338.7 2161.67  5346.0 2162.95  5388.7 2164.58
  5438.7 2168.18  5453.3 2170.26  5488.7 2171.93  5492.8 2172.90  5496.0 2172.90
#Mann=3,-1,0
  4837.9    0.07       0  5006.3    0.05       0  5012.8    0.07       0
Bank Sta=5006.3,5012.8
Exp/Cntr=0.3,0.1

Type RM Length L Ch R = 1,12327,546,546,546
BEGIN DESCRIPTION:
Stream0123 27.0
END DESCRIPTION:
XS GIS Cut Line= 3
      1784675.02     13948325.01      1784542.04     13948280.10
      1784175.01     13948075.01
#Sta/Elev= 30
  4840.6 2157.78  4903.9 2154.76  4935.6 2151.63  4950.7 2151.42  4976.8 2146.80
  4981.0 2146.67  4998.2 2142.82  5003.9 2143.39  5008.6 2141.68  5009.1 2141.18
  5015.2 2141.68  5019.9 2142.39  5034.8 2142.37  5041.6 2143.72  5069.2 2145.02
  5106.7 2144.83  5115.0 2145.54  5122.7 2147.44  5144.4 2149.70  5150.1 2149.62
  5160.4 2151.36  5166.1 2151.25  5172.3 2152.71  5187.8 2153.36  5247.2 2160.67
  5312.3 2166.93  5328.3 2170.69  5350.0 2173.80  5366.0 2175.13  5401.4 2176.16
#Mann=3,-1,0
  4840.6    0.07       0  5008.6    0.05       0  5015.2    0.07       0
Bank Sta=5008.6,5015.2
Exp/Cntr=0.3,0.1

Type RM Length L Ch R = 1,11781,424,424,424
BEGIN DESCRIPTION:
Stream0123 26.0
END DESCRIPTION:
XS GIS Cut Line= 3
      1784874.96     13947824.99      1784575.00     13947775.00
      1784475.00     13947725.00
#Sta/Elev= 30
  4691.7 2152.26  4719.5 2151.10  4724.6 2151.53  4780.4 2147.13  4793.0 2146.47
  4823.4 2145.87  4833.6 2144.66  4841.2 2144.64  4846.3 2144.08  4874.1 2142.88
  4914.7 2142.07  4945.1 2140.70  4955.2 2140.61  4962.8 2141.14  4993.3 2137.23
  4998.6 2137.23  5004.2 2135.57  5006.3 2134.53  5006.8 2134.03  5012.8 2134.03
  5013.3 2134.53  5018.2 2134.57  5026.5 2139.34  5032.1 2141.33  5040.5 2145.17
  5054.5 2149.44  5085.2 2154.77  5093.6 2156.63  5104.8 2158.05  5107.6 2158.05
#Mann=3,-1,0
  4691.7    0.07       0  5006.3    0.05       0  5013.3    0.07       0
Bank Sta=5006.3,5013.3
Exp/Cntr=0.3,0.1

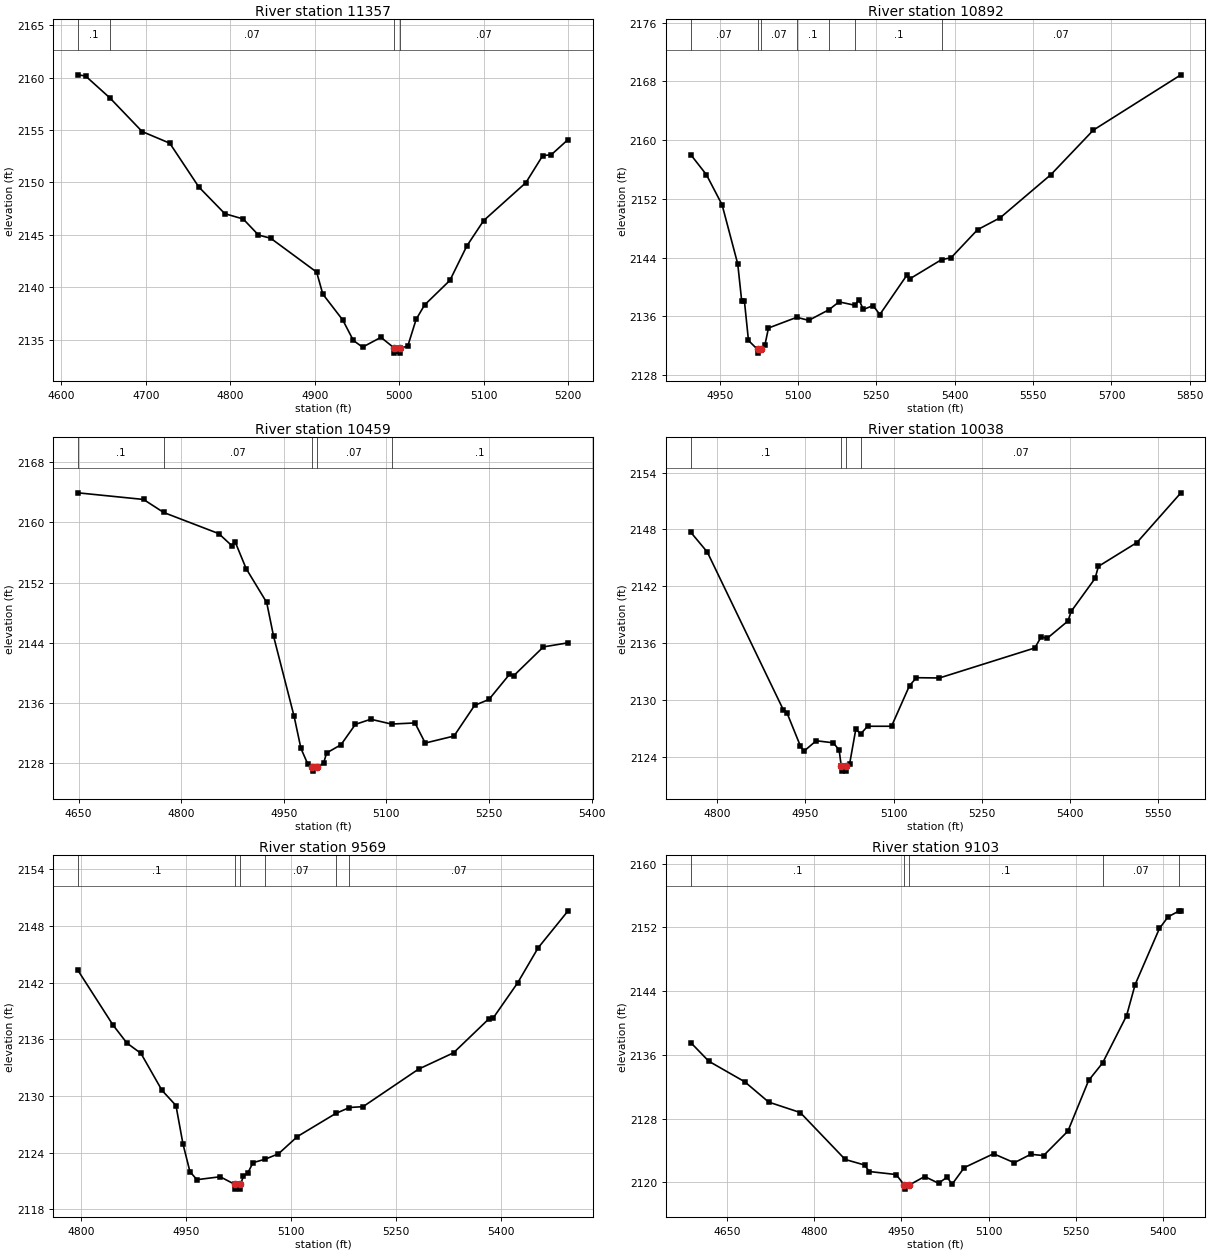
Type RM Length L Ch R = 1,11357,465,465,465
BEGIN DESCRIPTION:
Stream0123 25.0
END DESCRIPTION:
XS GIS Cut Line= 3
      1785124.96     13947574.98      1784775.00     13947425.00
      1784575.05     13947425.00
#Sta/Elev= 30
  4619.5 2160.28  4628.5 2160.17  4657.3 2158.08  4695.6 2154.86  4728.3 2153.75
  4762.7 2149.57  4793.5 2147.02  4815.3 2146.51  4833.4 2144.98  4847.9 2144.67
  4902.3 2141.44  4909.6 2139.34  4933.2 2136.87  4945.8 2134.91  4956.7 2134.27
  4978.5 2135.21  4994.0 2134.20  4994.5 2133.70  5000.5 2133.70  5001.0 2134.20
  5010.2 2134.35  5020.2 2136.93  5030.2 2138.30  5060.2 2140.65  5080.2 2143.93
  5100.2 2146.36  5150.2 2149.98  5170.2 2152.57  5180.2 2152.64  5200.2 2154.10
#Mann=4,-1,0
  4619.5     0.1       0  4657.3    0.07       0  4994.0    0.05       0
  5001.0    0.07       0
Bank Sta=4994,5001
Exp/Cntr=0.3,0.1

Type RM Length L Ch R = 1,10892,433,433,433
BEGIN DESCRIPTION:
Stream0123 24.0
END DESCRIPTION:
XS GIS Cut Line= 3
      1785175.03     13947075.00      1785075.00     13947075.00
      1784274.99     13947325.00
#Sta/Elev= 30
  4894.7 2158.03  4924.7 2155.30  4954.7 2151.20  4984.7 2143.13  4992.2 2138.12
  4997.4 2138.12  5005.2 2132.72  5022.6 2131.50  5023.1 2131.00  5029.7 2131.50
  5036.6 2132.09  5043.5 2134.42  5097.7 2135.88  5120.5 2135.46  5159.2 2136.91
  5178.6 2137.98  5209.6 2137.51  5216.3 2138.30  5225.2 2136.95  5243.6 2137.47
  5256.7 2136.26  5308.5 2141.63  5313.8 2141.11  5374.9 2143.74  5392.9 2143.98
  5443.7 2147.81  5487.1 2149.44  5584.1 2155.31  5665.3 2161.37  5832.9 2168.90
#Mann=7,-1,0
  4894.7    0.07       0  5022.6    0.05       0  5029.7    0.07       0
  5097.7     0.1       0  5159.2    0.07       0  5209.6     0.1       0
  5374.9    0.07       0
Bank Sta=5022.6,5029.7
Exp/Cntr=0.3,0.1

Type RM Length L Ch R = 1,10459,421,421,421
BEGIN DESCRIPTION:
Stream0123 23.0
END DESCRIPTION:
XS GIS Cut Line= 3
      1785330.83     13946689.01      1784975.00     13946675.00
      1784674.97     13946875.02
#Sta/Elev= 30
  4649.0 2163.92  4744.9 2163.04  4774.4 2161.31  4855.0 2158.50  4874.0 2156.90
  4879.0 2157.38  4895.0 2153.85  4925.0 2149.36  4935.1 2144.86  4965.1 2134.23
  4975.1 2129.97  4985.1 2127.90  4991.6 2127.46  4992.1 2126.96  4998.7 2127.46
  5008.1 2127.99  5012.6 2129.37  5033.7 2130.47  5054.7 2133.17  5077.2 2133.85
  5107.5 2133.21  5141.8 2133.36  5156.8 2130.69  5198.9 2131.62  5229.0 2135.69
  5250.0 2136.48  5280.0 2139.81  5286.0 2139.61  5329.6 2143.46  5365.7 2144.00
#Mann=5,-1,0
  4649.0     0.1       0  4774.4    0.07       0  4991.6    0.05       0
  4998.7    0.07       0  5107.5     0.1       0
Bank Sta=4991.6,4998.7
Exp/Cntr=0.3,0.1

Type RM Length L Ch R = 1,10038,469,469,469
BEGIN DESCRIPTION:
Stream0123 22.0
END DESCRIPTION:
XS GIS Cut Line= 3
      1784975.02     13946174.98      1784775.00     13946325.00
      1784201.62     13946436.77
#Sta/Elev= 30
  4754.7 2147.70  4782.9 2145.60  4912.0 2128.97  4918.3 2128.64  4941.2 2125.13
  4947.4 2124.57  4968.3 2125.67  4997.4 2125.45  5007.3 2124.68  5010.9 2122.96
  5011.4 2122.46  5018.4 2122.46  5018.9 2122.96  5025.1 2123.23  5035.6 2126.88
  5044.0 2126.40  5055.7 2127.20  5096.4 2127.20  5127.0 2131.49  5138.8 2132.33
  5177.9 2132.30  5340.2 2135.47  5351.1 2136.64  5361.3 2136.49  5396.7 2138.32
  5402.1 2139.33  5442.8 2142.82  5448.5 2144.09  5514.1 2146.61  5588.9 2151.86
#Mann=4,-1,0
  4754.7     0.1       0  5010.9    0.05       0  5018.9     0.1       0
  5044.0    0.07       0
Bank Sta=5010.9,5018.9
Exp/Cntr=0.3,0.1

Type RM Length L Ch R = 1,9569,466,466,466
BEGIN DESCRIPTION:
Stream0123 21.0
END DESCRIPTION:
XS GIS Cut Line= 3
      1784774.96     13945925.00      1784575.00     13945925.00
      1784174.96     13946225.03
#Sta/Elev= 30
  4795.3 2143.31  4845.3 2137.53  4865.3 2135.61  4885.3 2134.52  4915.3 2130.61
  4935.3 2129.00  4945.3 2124.94  4955.3 2121.99  4965.3 2121.15  4998.4 2121.46
  5019.4 2120.65  5019.9 2120.15  5026.9 2120.15  5027.4 2120.65  5031.7 2121.51
  5038.0 2121.87  5045.3 2122.95  5062.8 2123.32  5081.7 2123.89  5108.8 2125.72
  5163.5 2128.16  5183.1 2128.79  5202.5 2128.88  5281.7 2132.85  5331.7 2134.58
  5381.7 2138.14  5388.0 2138.23  5423.4 2142.00  5452.5 2145.69  5495.3 2149.61
#Mann=6,-1,0
  4795.3     0.1       0  5019.4    0.05       0  5027.4     0.1       0
  5062.8    0.07       0  5163.5     0.1       0  5183.1    0.07       0
Bank Sta=5019.4,5027.4
Exp/Cntr=0.3,0.1

Type RM Length L Ch R = 1,9103,479,479,479
BEGIN DESCRIPTION:
Stream0123 20.0
END DESCRIPTION:
XS GIS Cut Line= 3
      1784725.04     13945675.01      1784325.00     13945575.00
      1783974.98     13945825.02
#Sta/Elev= 30
  4588.0 2137.55  4619.0 2135.21  4680.8 2132.63  4722.0 2130.08  4776.2 2128.77
  4853.5 2122.88  4887.0 2122.18  4894.7 2121.37  4941.1 2120.99  4955.1 2119.66
  4955.6 2119.16  4963.2 2119.66  4990.0 2120.74  5013.9 2119.90  5028.6 2120.66
  5037.2 2119.77  5058.1 2121.86  5108.5 2123.60  5144.1 2122.47  5172.4 2123.53
  5194.5 2123.37  5236.3 2126.44  5271.9 2132.80  5295.8 2134.98  5337.1 2140.92
  5351.8 2144.82  5393.6 2151.87  5408.4 2153.32  5427.2 2154.06  5430.5 2154.08
#Mann=5,-1,0
  4588.0     0.1       0  4955.1    0.05       0  4963.2     0.1       0
  5295.8    0.07       0  5427.2     0.1       0
Bank Sta=4955.1,4963.2
Exp/Cntr=0.3,0.1

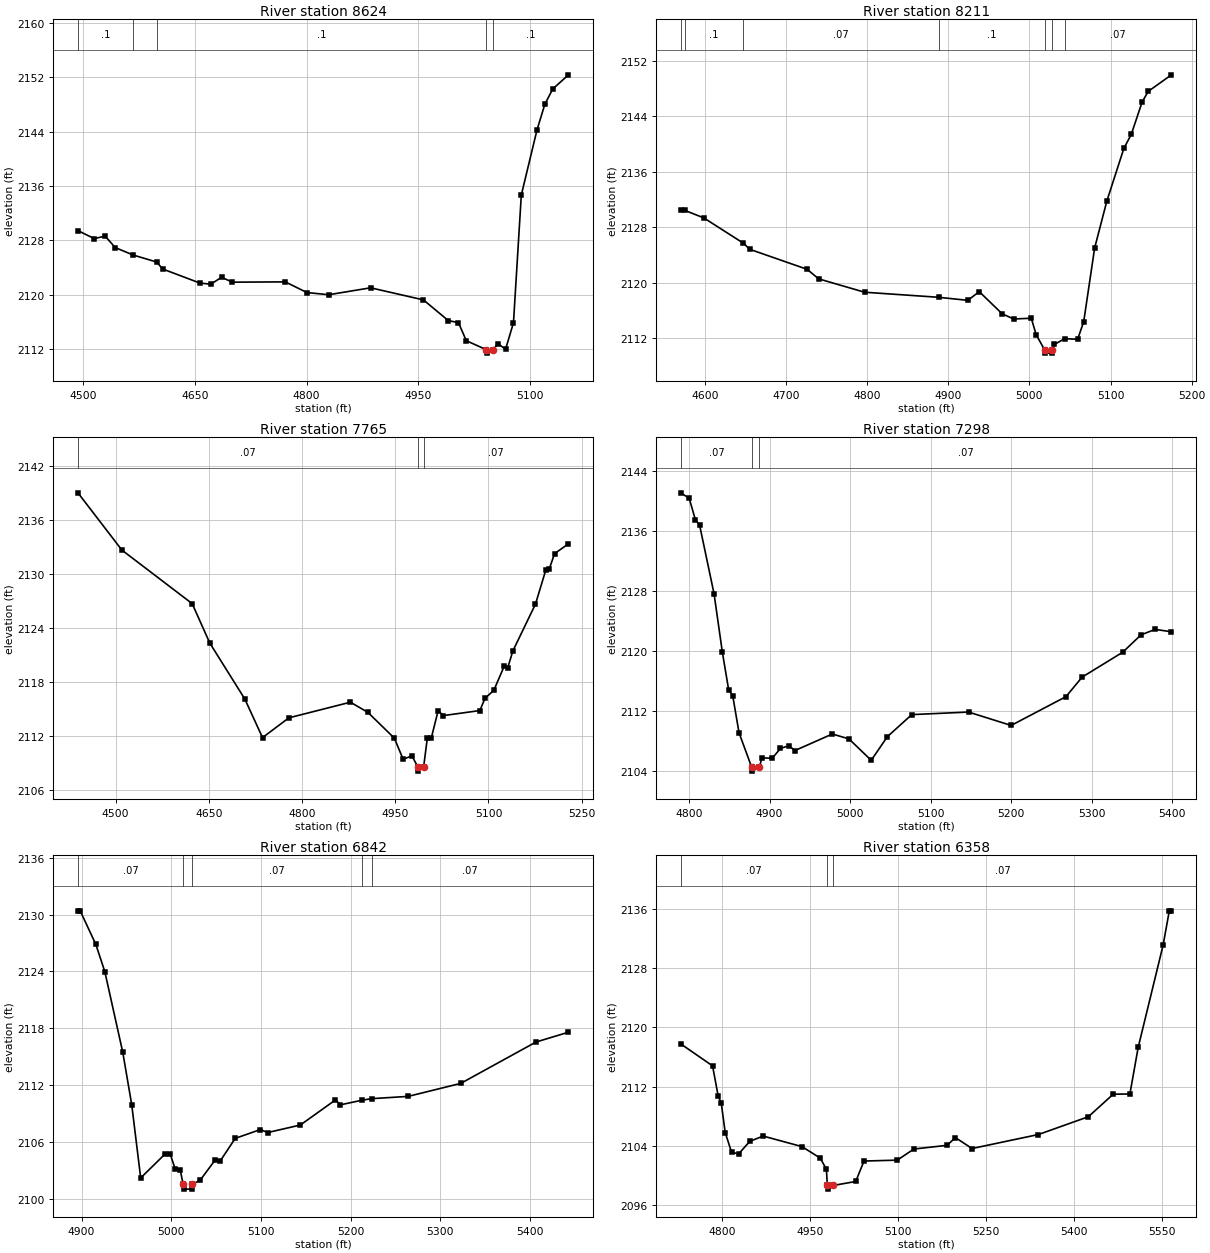
Type RM Length L Ch R = 1,8624,413,413,413
BEGIN DESCRIPTION:
Stream0123 19.0
END DESCRIPTION:
XS GIS Cut Line= 3
      1784625.03     13945475.02      1784225.00     13945175.00
      1784174.98     13945024.95
#Sta/Elev= 30
  4493.1 2129.43  4515.0 2128.26  4529.6 2128.62  4543.1 2126.94  4567.2 2125.84
  4598.8 2124.81  4606.7 2123.79  4656.7 2121.72  4671.3 2121.55  4685.8 2122.56
  4700.4 2121.85  4771.3 2121.89  4800.4 2120.32  4829.6 2120.00  4885.8 2121.02
  4956.7 2119.24  4990.0 2116.20  5003.7 2115.89  5014.2 2113.24  5041.1 2111.91
  5041.6 2111.41  5050.6 2111.91  5056.4 2112.82  5066.9 2111.98  5077.5 2115.89
  5088.0 2134.66  5109.1 2144.26  5119.6 2148.02  5130.2 2150.27  5151.3 2152.35
#Mann=5,-1,0
  4493.1     0.1       0  4567.2    0.07       0  4598.8     0.1       0
  5041.1    0.05       0  5050.6     0.1       0
Bank Sta=5041.1,5050.6
Exp/Cntr=0.3,0.1

Type RM Length L Ch R = 1,8211,446,446,446
BEGIN DESCRIPTION:
Stream0123 18.0
END DESCRIPTION:
XS GIS Cut Line= 3
      1784825.00     13945275.00      1784525.00     13944975.00
      1784375.03     13944875.02
#Sta/Elev= 30
  4570.5 2130.48  4575.1 2130.43  4598.8 2129.33  4647.6 2125.68  4655.3 2124.81
  4726.1 2121.92  4740.2 2120.55  4796.8 2118.62  4888.1 2117.89  4924.0 2117.45
  4938.2 2118.70  4966.5 2115.50  4980.6 2114.76  5002.3 2114.87  5008.3 2112.50
  5018.6 2110.34  5019.1 2109.84  5027.6 2109.84  5028.1 2110.34  5030.8 2111.09
  5043.5 2111.93  5059.4 2111.83  5066.9 2114.37  5080.4 2125.01  5095.4 2131.76
  5116.4 2139.36  5125.5 2141.37  5139.0 2146.08  5146.5 2147.58  5175.0 2149.96
#Mann=7,-1,0
  4570.5    0.07       0  4575.1     0.1       0  4647.6    0.07       0
  4888.1     0.1       0  5018.6    0.05       0  5028.1     0.1       0
  5043.5    0.07       0
Bank Sta=5018.6,5028.1
Exp/Cntr=0.3,0.1

Type RM Length L Ch R = 1,7765,467,467,467
BEGIN DESCRIPTION:
Stream0123 17.0
END DESCRIPTION:
XS GIS Cut Line= 3
      1785224.98     13945074.98      1784825.00     13944675.00
      1784624.96     13944574.98
#Sta/Elev= 30
  4439.4 2139.06  4510.1 2132.69  4623.2 2126.73  4651.5 2122.35  4708.1 2116.09
  4736.4 2111.82  4778.8 2114.02  4877.8 2115.76  4906.1 2114.62  4948.5 2111.76
  4962.6 2109.42  4976.8 2109.78  4986.1 2108.59  4986.6 2108.09  4995.7 2108.59
  5001.5 2111.73  5007.8 2111.73  5019.0 2114.82  5027.4 2114.27  5086.1 2114.83
  5094.5 2116.21  5108.5 2117.07  5125.2 2119.76  5130.8 2119.56  5139.2 2121.46
  5175.6 2126.68  5192.3 2130.49  5197.9 2130.61  5206.3 2132.29  5228.7 2133.39
#Mann=3,-1,0
  4439.4    0.07       0  4986.1    0.05       0  4995.7    0.07       0
Bank Sta=4986.1,4995.7
Exp/Cntr=0.3,0.1

Type RM Length L Ch R = 1,7298,456,456,456
BEGIN DESCRIPTION:
Stream0123 16.0
END DESCRIPTION:
XS GIS Cut Line= 3
      1785375.00     13944325.00      1785175.00     13944375.00
      1784774.96     13944325.00
#Sta/Elev= 30
  4789.8 2141.04  4800.1 2140.31  4807.8 2137.46  4813.0 2136.76  4831.0 2127.60
  4841.3 2119.84  4849.1 2114.85  4854.2 2114.03  4862.0 2109.12  4877.8 2104.51
  4878.3 2104.01  4887.4 2104.51  4890.3 2105.78  4903.2 2105.72  4913.5 2107.03
  4923.8 2107.39  4931.5 2106.75  4977.9 2108.95  4998.5 2108.30  5026.2 2105.45
  5046.3 2108.60  5076.6 2111.53  5147.1 2111.87  5200.0 2110.09  5268.1 2113.92
  5288.2 2116.52  5338.6 2119.83  5361.3 2122.14  5378.9 2122.87  5399.1 2122.55
#Mann=3,-1,0
  4789.8    0.07       0  4877.8    0.05       0  4887.4    0.07       0
Bank Sta=4877.8,4887.4
Exp/Cntr=0.3,0.1

Type RM Length L Ch R = 1,6842,484,484,484
BEGIN DESCRIPTION:
Stream0123 15.0
END DESCRIPTION:
XS GIS Cut Line= 3
      1785374.98     13943975.00      1785275.00     13943975.00
      1784875.00     13944175.00
#Sta/Elev= 30
  4895.9 2130.39  4898.4 2130.39  4915.9 2126.84  4925.9 2123.97  4945.9 2115.47
  4955.9 2109.94  4965.9 2102.22  4993.4 2104.77  4998.7 2104.77  5004.3 2103.18
  5009.9 2103.10  5013.3 2101.54  5013.8 2101.04  5022.6 2101.04  5023.1 2101.54
  5032.2 2101.97  5049.0 2104.12  5054.6 2104.00  5071.3 2106.39  5099.3 2107.32
  5107.7 2107.01  5144.0 2107.80  5183.2 2110.45  5188.7 2109.93  5212.4 2110.41
  5223.4 2110.58  5264.2 2110.82  5322.9 2112.19  5406.8 2116.55  5443.1 2117.59
#Mann=5,-1,0
  4895.9    0.07       0  5013.3    0.05       0  5023.1    0.07       0
  5212.4   0.035       0  5223.4    0.07       0
Bank Sta=5013.3,5023.1
Exp/Cntr=0.3,0.1

Type RM Length L Ch R = 1,6358,457,457,457
BEGIN DESCRIPTION:
Stream0123 14.0
END DESCRIPTION:
XS GIS Cut Line= 3
      1785425.03     13943625.01      1785175.00     13943525.00
      1784774.98     13943124.98
#Sta/Elev= 30
  4730.5 2117.76  4784.4 2114.81  4793.8 2110.81  4799.2 2109.80  4805.9 2105.82
  4816.7 2103.17  4828.8 2102.93  4847.7 2104.62  4870.5 2105.34  4936.5 2103.92
  4967.5 2102.38  4978.2 2100.87  4979.8 2098.68  4980.3 2098.18  4990.1 2098.68
  5028.1 2099.21  5042.2 2101.97  5098.8 2102.09  5127.1 2103.59  5183.6 2104.09
  5197.8 2105.13  5226.1 2103.66  5339.2 2105.55  5424.1 2107.95  5466.5 2110.99
  5494.8 2111.02  5508.9 2117.30  5551.3 2131.09  5561.9 2135.73  5565.5 2135.73
#Mann=3,-1,0
  4730.5    0.07       0  4979.8    0.05       0  4990.1    0.07       0
Bank Sta=4979.8,4990.1
Exp/Cntr=0.3,0.1

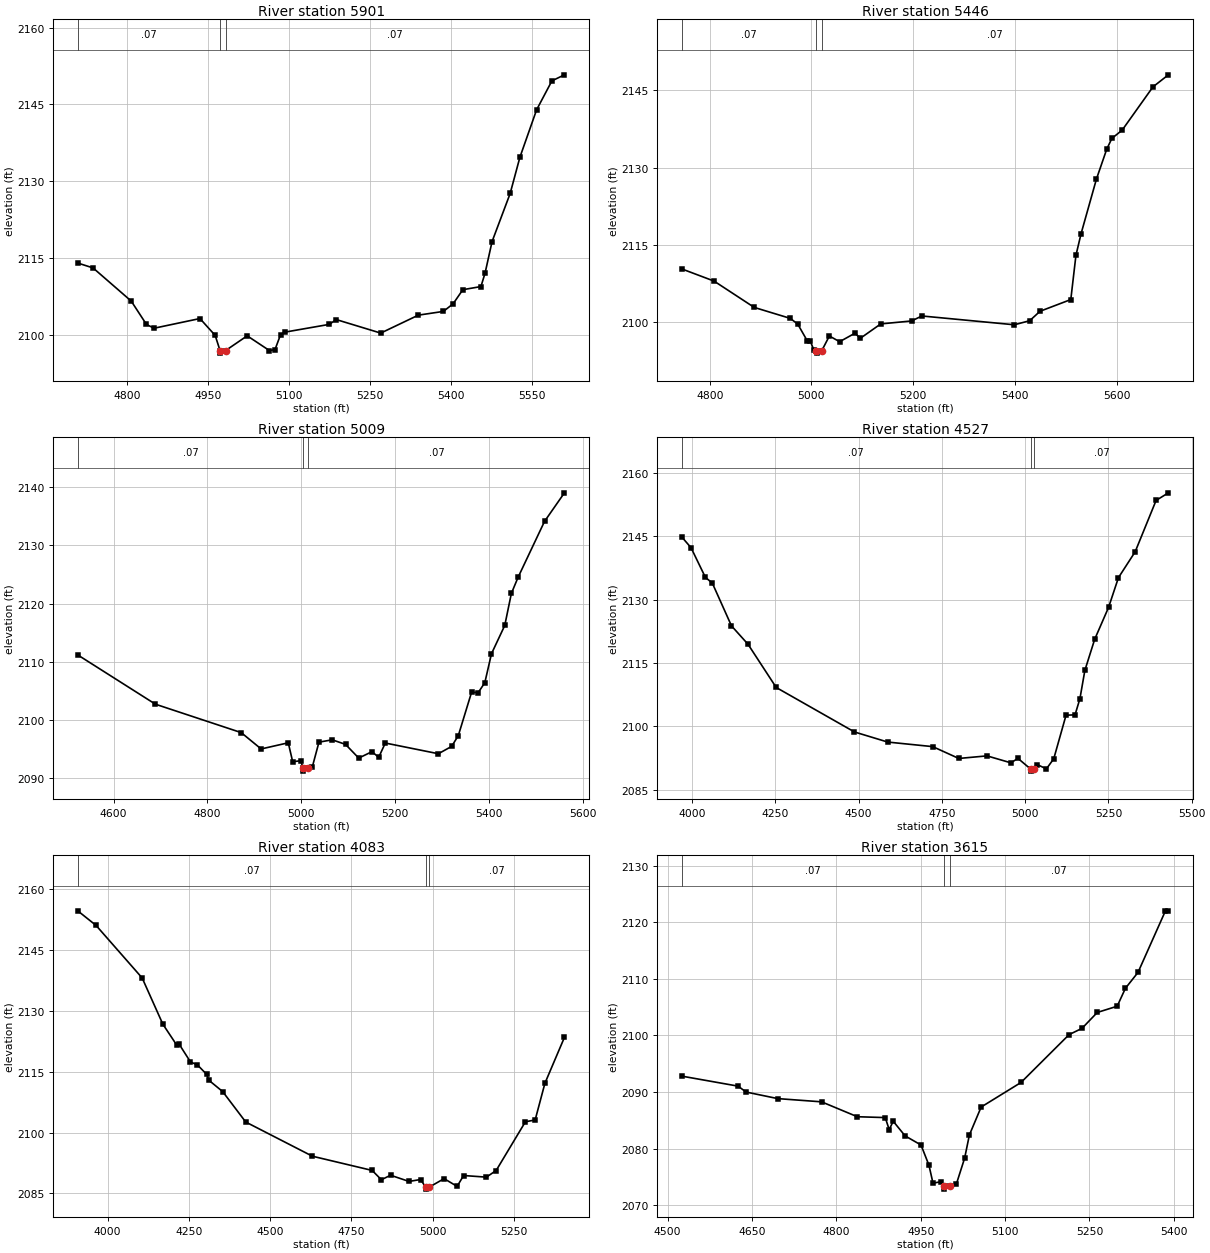
Type RM Length L Ch R = 1,5901,455,455,455
BEGIN DESCRIPTION:
Stream0123 13.0
END DESCRIPTION:
XS GIS Cut Line= 3
      1785524.99     13943374.99      1785325.00     13943175.00
      1784724.99     13943025.00
#Sta/Elev= 30
  4708.9 2114.06  4737.2 2113.11  4807.9 2106.64  4836.2 2102.07  4850.3 2101.34
  4935.2 2103.23  4963.4 2099.94  4972.4 2096.98  4972.9 2096.48  4982.7 2096.98
  5022.7 2099.86  5063.9 2096.98  5074.2 2097.17  5084.5 2100.08  5092.2 2100.57
  5174.7 2102.09  5187.6 2103.03  5270.0 2100.39  5339.6 2103.89  5386.0 2104.62
  5404.0 2106.10  5422.1 2108.86  5455.6 2109.47  5463.3 2112.13  5476.2 2118.25
  5509.7 2127.64  5527.7 2134.69  5558.7 2143.97  5587.0 2149.61  5610.2 2150.79
#Mann=3,-1,0
  4708.9    0.07       0  4972.4    0.05       0  4982.7    0.07       0
Bank Sta=4972.4,4982.7
Exp/Cntr=0.3,0.1

Type RM Length L Ch R = 1,5446,437,437,437
BEGIN DESCRIPTION:
Stream0123 12.0
END DESCRIPTION:
XS GIS Cut Line= 3
      1785675.03     13942925.02      1785475.00     13942775.00
      1784775.04     13942874.99
#Sta/Elev= 30
  4744.9 2110.33  4808.5 2107.96  4887.6 2102.84  4958.5 2100.71  4973.1 2099.60
  4991.8 2096.35  4997.5 2096.35  5005.0 2094.53  5009.7 2094.46  5010.2 2093.96
  5020.5 2094.46  5035.3 2097.29  5055.5 2096.18  5085.8 2097.84  5096.0 2096.83
  5136.4 2099.64  5197.0 2100.21  5217.2 2101.18  5399.0 2099.47  5429.3 2100.26
  5449.5 2102.09  5510.1 2104.37  5520.2 2112.96  5530.3 2117.17  5560.6 2127.81
  5580.8 2133.60  5590.9 2135.69  5611.1 2137.29  5671.7 2145.70  5702.0 2148.04
#Mann=3,-1,0
  4744.9    0.07       0  5009.7    0.05       0  5020.5    0.07       0
Bank Sta=5009.7,5020.5
Exp/Cntr=0.3,0.1

Type RM Length L Ch R = 1,5009,482,482,482
BEGIN DESCRIPTION:
Stream0123 11.0
END DESCRIPTION:
XS GIS Cut Line= 3
      1785974.97     13942624.98      1785575.00     13942375.00
      1785175.03     13941975.03
#Sta/Elev= 30
  4523.8 2111.19  4689.4 2102.72  4872.2 2097.84  4914.7 2095.03  4972.5 2096.09
  4981.9 2092.83  4999.0 2093.01  5004.2 2091.72  5004.7 2091.22  5015.1 2091.72
  5023.7 2091.92  5037.9 2096.20  5066.2 2096.60  5094.5 2095.82  5122.7 2093.46
  5151.0 2094.57  5165.2 2093.58  5179.3 2096.05  5292.4 2094.21  5320.7 2095.47
  5334.9 2097.32  5363.2 2104.78  5377.3 2104.71  5391.4 2106.42  5405.6 2111.39
  5433.9 2116.25  5448.0 2121.76  5462.2 2124.51  5518.7 2134.14  5561.1 2139.05
#Mann=3,-1,0
  4523.8    0.07       0  5004.2    0.05       0  5015.1    0.07       0
Bank Sta=5004.2,5015.1
Exp/Cntr=0.3,0.1

Type RM Length L Ch R = 1,4527,444,444,444
BEGIN DESCRIPTION:
Stream0123 10.0
END DESCRIPTION:
XS GIS Cut Line= 3
      1786374.99     13942574.99      1785575.00     13941925.00
      1785224.99     13941674.99
#Sta/Elev= 30
  3969.2 2144.83  3997.2 2142.27  4040.3 2135.25  4061.1 2133.89  4118.6 2123.77
  4168.2 2119.42  4252.9 2109.18  4487.8 2098.65  4587.7 2096.26  4722.7 2095.18
  4801.0 2092.38  4885.7 2092.99  4957.6 2091.34  4978.4 2092.41  5016.5 2089.88
  5017.0 2089.38  5027.7 2089.88  5036.8 2090.92  5063.9 2089.91  5086.0 2092.30
  5122.9 2102.62  5149.9 2102.70  5164.6 2106.54  5179.4 2113.22  5208.9 2120.59
  5250.7 2128.17  5280.2 2135.18  5330.5 2141.32  5393.2 2153.46  5430.1 2155.26
#Mann=3,-1,0
  3969.2    0.07       0  5016.5    0.05       0  5027.7    0.07       0
Bank Sta=5016.5,5027.7
Exp/Cntr=0.3,0.1

Type RM Length L Ch R = 1,4083,468,468,468
BEGIN DESCRIPTION:
Stream0123 9.0
END DESCRIPTION:
XS GIS Cut Line= 3
      1786625.01     13942425.01      1785875.00     13941625.00
      1785475.00     13941625.00
#Sta/Elev= 30
  3908.4 2154.58  3964.8 2150.98  4106.5 2138.05  4170.0 2126.69  4212.5 2121.56
  4219.8 2121.80  4255.0 2117.39  4276.5 2116.64  4304.8 2114.33  4311.6 2112.87
  4354.1 2110.08  4425.0 2102.59  4630.1 2094.17  4813.8 2090.67  4842.1 2088.38
  4870.4 2089.49  4927.1 2087.96  4962.7 2088.44  4978.1 2086.57  4978.6 2086.07
  4989.4 2086.57  5035.0 2088.65  5075.0 2086.75  5095.0 2089.42  5165.0 2089.02
  5195.0 2090.65  5285.0 2102.65  5315.0 2103.10  5345.0 2112.13  5405.0 2123.42
#Mann=3,-1,0
  3908.4    0.07       0  4978.1    0.05       0  4989.4    0.07       0
Bank Sta=4978.1,4989.4
Exp/Cntr=0.3,0.1

Type RM Length L Ch R = 1,3615,425,425,425
BEGIN DESCRIPTION:
Stream0123 8.0
END DESCRIPTION:
XS GIS Cut Line= 3
      1786467.57     13941604.04      1786125.00     13941275.00
      1785811.69     13941042.25
#Sta/Elev= 30
  4525.0 2092.82  4625.3 2091.05  4639.4 2090.01  4695.8 2088.85  4773.7 2088.28
  4837.3 2085.65  4886.9 2085.50  4893.9 2083.39  4901.1 2084.85  4922.2 2082.27
  4950.5 2080.66  4964.6 2077.09  4971.8 2073.92  4986.0 2074.18  4990.8 2073.37
  4991.3 2072.87  5002.2 2073.37  5013.5 2073.81  5028.1 2078.36  5036.5 2082.43
  5057.4 2087.36  5128.3 2091.70  5213.8 2100.15  5236.7 2101.25  5263.9 2104.06
  5299.3 2105.16  5313.9 2108.32  5336.3 2111.13  5385.1 2122.00  5390.3 2122.00
#Mann=3,-1,0
  4525.0    0.07       0  4990.8    0.05       0  5002.2    0.07       0
Bank Sta=4990.8,5002.2
Exp/Cntr=0.3,0.1

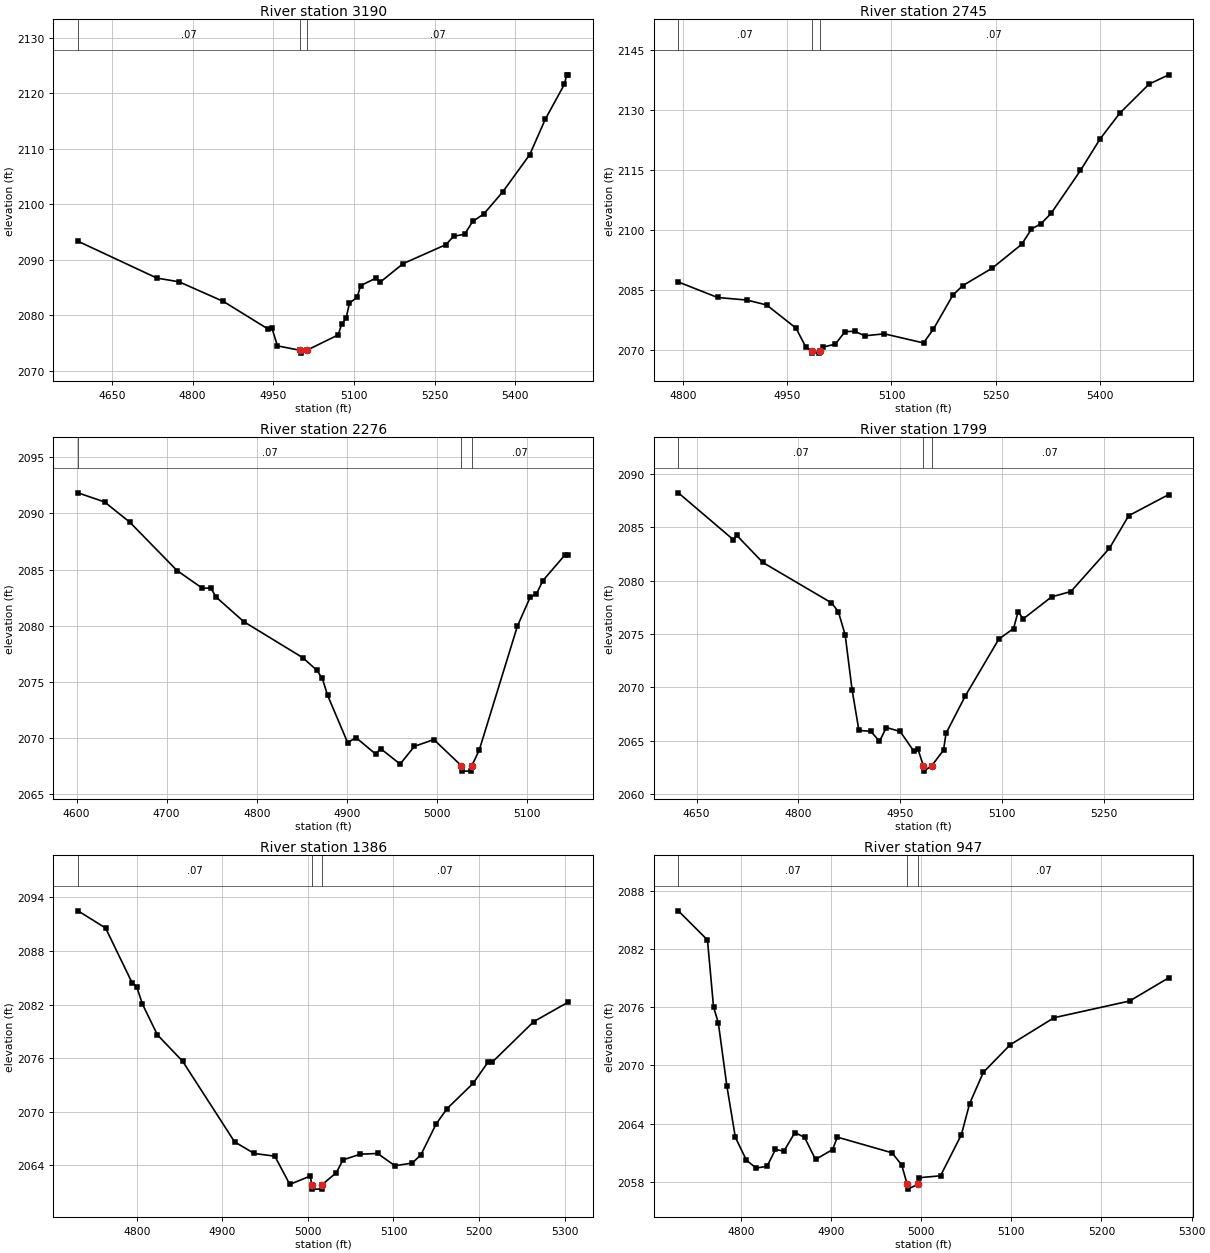
Type RM Length L Ch R = 1,3190,445,445,445
BEGIN DESCRIPTION:
Stream0123 7.0
END DESCRIPTION:
XS GIS Cut Line= 3
      1786724.99     13941025.00      1786325.00     13940925.00
      1786025.00     13940525.00
#Sta/Elev= 30
  4586.6 2093.37  4733.5 2086.73  4774.7 2086.06  4857.2 2082.52  4939.6 2077.59
  4947.4 2077.75  4957.7 2074.52  5000.3 2073.71  5000.8 2073.21  5012.1 2073.71
  5070.8 2076.50  5077.0 2078.42  5085.4 2079.47  5091.6 2082.19  5106.2 2083.32
  5112.4 2085.37  5141.6 2086.75  5148.9 2086.00  5191.6 2089.34  5270.8 2092.74
  5285.4 2094.25  5306.2 2094.65  5320.8 2096.93  5341.6 2098.28  5377.0 2102.28
  5427.0 2108.96  5456.2 2115.39  5491.6 2121.65  5495.8 2123.35  5498.9 2123.35
#Mann=3,-1,0
  4586.6    0.07       0  5000.3    0.05       0  5012.1    0.07       0
Bank Sta=5000.3,5012.1
Exp/Cntr=0.3,0.1

Type RM Length L Ch R = 1,2745,469,469,469
BEGIN DESCRIPTION:
Stream0123 6.0
END DESCRIPTION:
XS GIS Cut Line= 3
      1786724.99     13940724.99      1786575.00     13940575.00
      1786225.00     13940225.00
#Sta/Elev= 30
  4792.7 2086.92  4849.3 2083.04  4891.7 2082.39  4920.0 2081.17  4962.4 2075.36
  4976.5 2070.63  4984.7 2069.61  4985.2 2069.11  4996.1 2069.11  4996.6 2069.61
  5001.3 2070.63  5019.0 2071.35  5033.1 2074.50  5047.2 2074.57  5061.4 2073.45
  5089.7 2073.94  5146.2 2071.66  5160.4 2075.10  5188.7 2083.67  5202.8 2086.01
  5245.2 2090.38  5287.7 2096.33  5301.8 2100.16  5315.9 2101.55  5330.1 2104.08
  5372.5 2114.84  5400.8 2122.73  5429.1 2129.16  5471.5 2136.47  5499.8 2138.78
#Mann=3,-1,0
  4792.7    0.07       0  4984.7    0.05       0  4996.6    0.07       0
Bank Sta=4984.7,4996.6
Exp/Cntr=0.3,0.1

Type RM Length L Ch R = 1,2276,477,477,477
BEGIN DESCRIPTION:
Stream0123 5.0
END DESCRIPTION:
XS GIS Cut Line= 3
      1787124.97     13940374.98      1786775.00     13940175.00
      1786675.00     13940075.00
#Sta/Elev= 30
  4601.5 2091.84  4631.0 2091.03  4659.0 2089.23  4711.6 2084.91  4739.7 2083.34
  4749.0 2083.36  4754.8 2082.56  4785.7 2080.36  4851.2 2077.15  4866.4 2076.06
  4872.8 2075.32  4878.6 2073.82  4900.9 2069.60  4910.3 2070.03  4931.9 2068.58
  4937.6 2069.05  4959.2 2067.68  4975.1 2069.26  4996.7 2069.86  5026.9 2067.55
  5027.4 2067.05  5038.4 2067.05  5038.9 2067.55  5047.0 2068.91  5089.4 2079.96
  5103.6 2082.54  5110.6 2082.84  5117.7 2084.02  5142.5 2086.33  5146.0 2086.33
#Mann=3,-1,0
  4601.5    0.07       0  5026.9    0.05       0  5038.9    0.07       0
Bank Sta=5026.9,5038.9
Exp/Cntr=0.3,0.1

Type RM Length L Ch R = 1,1799,413,413,413
BEGIN DESCRIPTION:
Stream0123 4.0
END DESCRIPTION:
XS GIS Cut Line= 3
      1787458.18     13939882.31      1787075.00     13939825.00
      1786825.07     13939601.53
#Sta/Elev= 30
  4623.2 2088.21  4704.3 2083.82  4709.4 2084.22  4747.7 2081.69  4848.9 2077.91
  4859.0 2077.09  4869.1 2074.89  4879.2 2069.79  4889.3 2065.97  4906.8 2065.89
  4919.6 2064.95  4929.7 2066.24  4950.0 2065.88  4970.2 2064.03  4976.0 2064.27
  4984.3 2062.66  4984.8 2062.16  4996.6 2062.66  5014.0 2064.13  5017.7 2065.70
  5046.2 2069.21  5095.5 2074.52  5117.2 2075.51  5123.9 2077.09  5131.4 2076.41
  5173.2 2078.47  5201.7 2078.97  5258.5 2083.02  5286.9 2086.07  5345.9 2088.05
#Mann=3,-1,0
  4623.2    0.07       0  4984.3    0.05       0  4996.6    0.07       0
Bank Sta=4984.3,4996.6
Exp/Cntr=0.3,0.1

Type RM Length L Ch R = 1,1386,439,439,439
BEGIN DESCRIPTION:
Stream0123 3.0
END DESCRIPTION:
XS GIS Cut Line= 3
      1787574.99     13939625.00      1787325.00     13939525.00
      1787024.99     13939475.00
#Sta/Elev= 30
  4731.1 2092.50  4763.4 2090.58  4794.4 2084.45  4799.8 2084.01  4806.5 2082.06
  4824.0 2078.62  4853.6 2075.65  4914.2 2066.65  4937.1 2065.34  4961.3 2065.04
  4978.8 2061.88  5002.9 2062.82  5004.3 2061.85  5004.8 2061.35  5016.1 2061.35
  5016.6 2061.85  5033.3 2063.20  5040.9 2064.62  5061.2 2065.26  5081.5 2065.34
  5101.7 2063.97  5122.0 2064.27  5132.1 2065.19  5149.9 2068.64  5162.6 2070.35
  5193.0 2073.18  5210.7 2075.58  5215.8 2075.59  5263.9 2080.09  5304.5 2082.29
#Mann=3,-1,0
  4731.1    0.07       0  5004.3    0.05       0  5016.6    0.07       0
Bank Sta=5004.3,5016.6
Exp/Cntr=0.3,0.1

Type RM Length L Ch R = 1,947,450,450,450
BEGIN DESCRIPTION:
Stream0123 2.0
END DESCRIPTION:
XS GIS Cut Line= 3
      1787624.97     13939224.99      1787375.00     13939125.00
      1787119.67     13939024.03
#Sta/Elev= 30
  4730.8 2085.91  4763.1 2082.91  4769.8 2076.05  4775.2 2074.34  4784.6 2067.89
  4794.0 2062.61  4806.2 2060.26  4816.9 2059.44  4829.1 2059.61  4838.5 2061.35
  4847.9 2061.18  4860.0 2063.09  4870.8 2062.60  4882.9 2060.32  4901.8 2061.34
  4907.1 2062.62  4967.7 2061.01  4978.5 2059.75  4984.5 2057.77  4985.0 2057.27
  4996.8 2057.77  4997.3 2058.44  5021.5 2058.64  5044.6 2062.86  5053.8 2066.07
  5069.0 2069.29  5098.7 2072.12  5147.4 2074.91  5231.2 2076.63  5274.6 2079.02
#Mann=3,-1,0
  4730.8    0.07       0  4984.5    0.05       0  4996.8    0.07       0
Bank Sta=4984.5,4996.8
Exp/Cntr=0.3,0.1

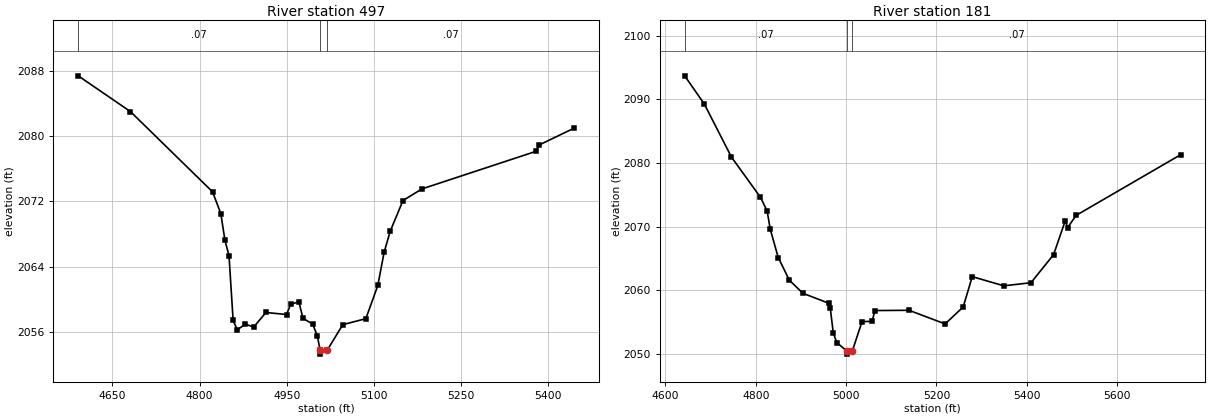
Type RM Length L Ch R = 1,497,316,316,316
BEGIN DESCRIPTION:
Stream0123 1.0
END DESCRIPTION:
XS GIS Cut Line= 3
      1787857.92     13939059.08      1787575.00     13938775.00
      1787142.24     13938642.57
#Sta/Elev= 30
  4591.0 2087.44  4680.8 2083.05  4822.2 2073.18  4836.4 2070.51  4843.4 2067.27
  4850.5 2065.33  4857.6 2057.38  4864.7 2056.22  4878.8 2056.92  4892.9 2056.55
  4914.1 2058.35  4949.5 2058.10  4956.6 2059.34  4970.7 2059.67  4977.8 2057.64
  4994.5 2056.92  5002.4 2055.50  5007.3 2053.73  5007.8 2053.23  5019.7 2053.73
  5046.3 2056.85  5086.0 2057.59  5106.6 2061.67  5117.4 2065.73  5127.9 2068.33
  5149.9 2072.11  5182.6 2073.54  5378.9 2078.16  5384.5 2078.95  5444.5 2081.01
#Mann=3,-1,0
  4591.0    0.07       0  5007.3    0.05       0  5019.7    0.07       0
Bank Sta=5007.3,5019.7
Exp/Cntr=0.3,0.1

Type RM Length L Ch R = 1,181,0,0,0
BEGIN DESCRIPTION:
Stream0123 0.0
END DESCRIPTION:
XS GIS Cut Line= 4
      1787975.38     13938941.51      1787860.36     13938644.21
      1787754.02     13938555.23      1787113.81     13938546.55
#Sta/Elev= 30
  4642.7 2093.69  4686.3 2089.25  4746.2 2080.94  4810.5 2074.62  4825.2 2072.48
  4832.0 2069.64  4849.8 2065.17  4874.4 2061.61  4904.4 2059.56  4961.5 2058.00
  4965.0 2057.21  4971.5 2053.39  4979.3 2051.82  5001.4 2050.51  5001.9 2050.01
  5013.8 2050.51  5035.3 2055.12  5057.4 2055.15  5063.9 2056.85  5139.2 2056.89
  5219.2 2054.75  5259.2 2057.42  5279.2 2062.17  5349.2 2060.73  5409.2 2061.22
  5459.2 2065.62  5485.2 2070.97  5490.2 2069.86  5509.2 2071.79  5740.4 2081.31
#Mann=3,-1,0
  4642.7    0.07       0  5001.4    0.05       0  5013.8    0.07       0
Bank Sta=5001.4,5013.8
Exp/Cntr=0.3,0.1

Chan Stop Cuts=-1