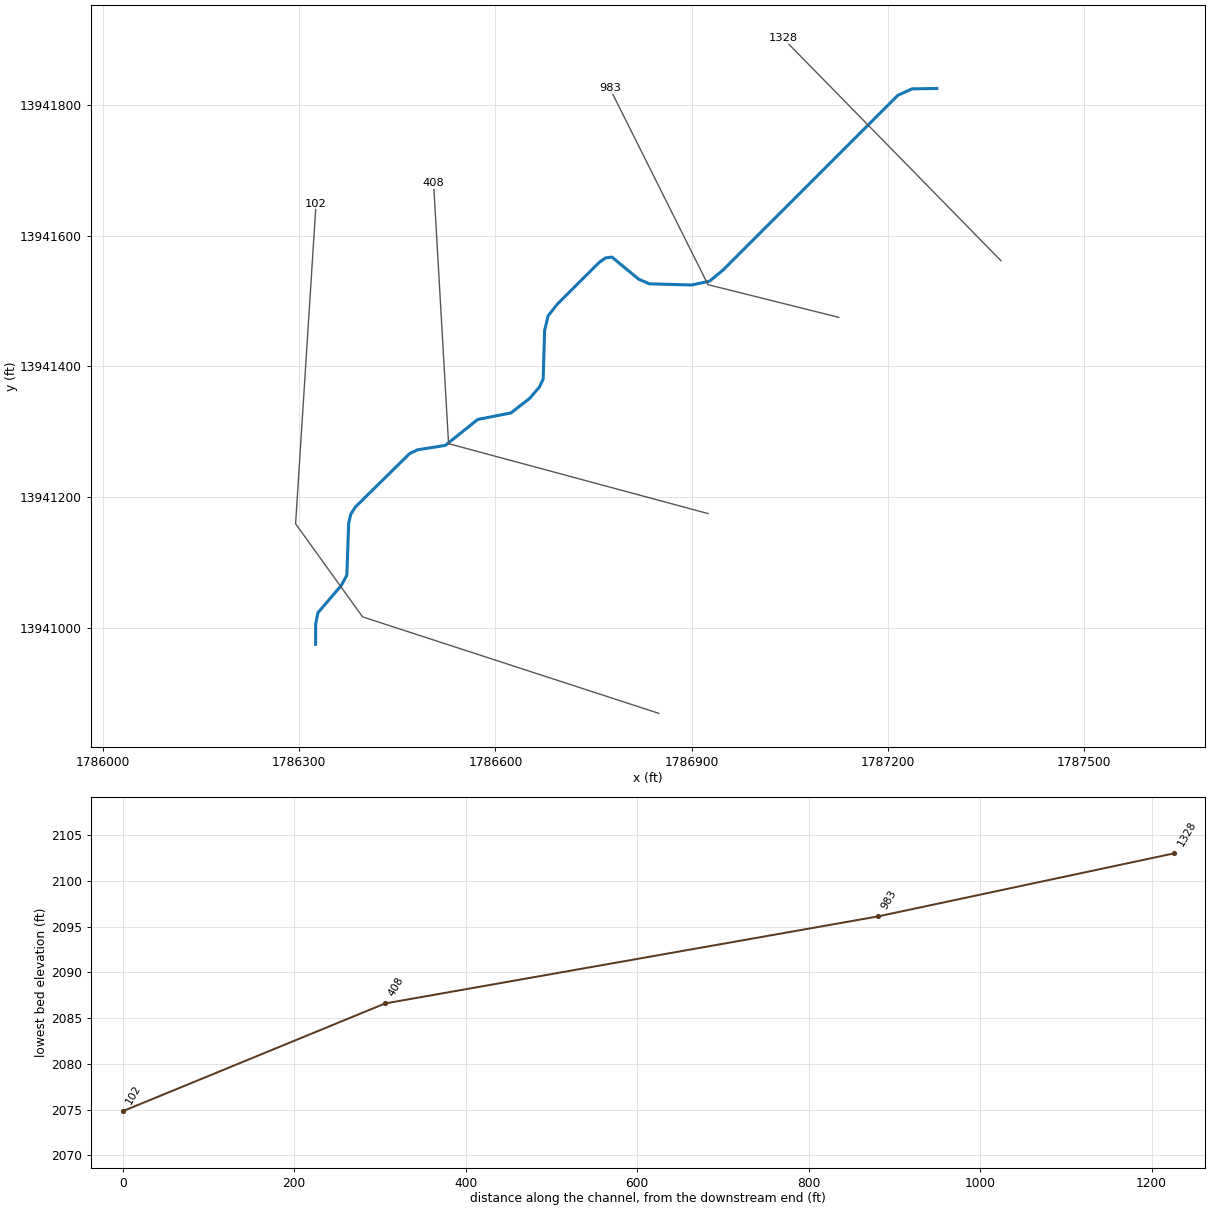
--- Stream0124.prj (project) ---

Proj Title=Stream0124 Base Level Engineering
Current Plan=p01
Default Exp/Contr=0.3,0.1
English Units
Geom File=g01
Flow File=f01
Plan File=p01
BEGIN DESCRIPTION:
Stream0124
END DESCRIPTION:

--- Stream0124.p01 (plan) ---

Plan Title=Multiple Run
Short Identifier=Multiple
Geom File=g01
Flow File=f01
Subcritical Flow
K Sum by GR= 0
Std Step Tol= 0.01
Critical Tol= 0.01
Num of Std Step Trials= 20
Max Error Tol= 0.3
Flow Tol Ratio= 0.001
Split Flow NTrial= 30
Split Flow Tol= 0.02
Split Flow Ratio= 0.02
Log Output Level= 0
Friction Slope Method= 1
Unsteady Friction Slope Method= 2
Unsteady Bridges Friction Slope Method= 1
Parabolic Critical Depth
Global Vel Dist=  1 , 1 , 1
Global Log Level= 0
CheckData=True
Encroach Param= -1, 0, 0, 0
BEGIN DESCRIPTION:
Multiple Run
END DESCRIPTION:

--- Stream0124.f01 (steady flow) ---

Flow Title=Multiple
Number of Profiles=7
Profile Names=10-year,25-year,50-year,1pct_min,100-year,1pct_plu,500-year
River Rch & RM= Stream0124,Reach-1,1328
     419     680     917     600    1197    2389    2013
Boundary for River Rch & Prof#=Stream0124,Reach-1,1
Up Type=0
Dn Type=3
Dn Slope=0.005
Boundary for River Rch & Prof#=Stream0124,Reach-1,2
Up Type=0
Dn Type=3
Dn Slope=0.005
Boundary for River Rch & Prof#=Stream0124,Reach-1,3
Up Type=0
Dn Type=3
Dn Slope=0.005
Boundary for River Rch & Prof#=Stream0124,Reach-1,4
Up Type=0
Dn Type=3
Dn Slope=0.005
Boundary for River Rch & Prof#=Stream0124,Reach-1,5
Up Type=0
Dn Type=3
Dn Slope=0.005
Boundary for River Rch & Prof#=Stream0124,Reach-1,6
Up Type=0
Dn Type=3
Dn Slope=0.005
Boundary for River Rch & Prof#=Stream0124,Reach-1,7
Up Type=0
Dn Type=3
Dn Slope=0.005

--- Stream0124.g01 (geometry) ---

Geom Title=Existing Conditions

River Reach=Stream0124,Reach-1
Reach XY= 30
      1787275.00     13941825.00      1787236.84     13941824.41
      1787215.21     13941814.49      1786948.52     13941547.84
      1786927.43     13941530.40      1786900.04     13941524.51
      1786835.48     13941526.27      1786818.83     13941533.42
      1786778.21     13941567.13      1786768.24     13941565.88
      1786758.26     13941558.72      1786694.63     13941495.24
      1786680.53     13941477.45      1786675.14     13941454.95
      1786672.92     13941380.71      1786667.25     13941368.54
      1786652.28     13941351.10      1786623.61     13941328.85
      1786572.84     13941318.89      1786523.26     13941279.19
      1786481.03     13941272.51      1786468.93     13941266.87
      1786385.51     13941184.81      1786378.60     13941173.52
      1786375.51     13941159.79      1786372.77     13941080.92
      1786364.38     13941065.26      1786328.64     13941023.49
      1786325.12     13941006.80      1786325.00     13940975.00

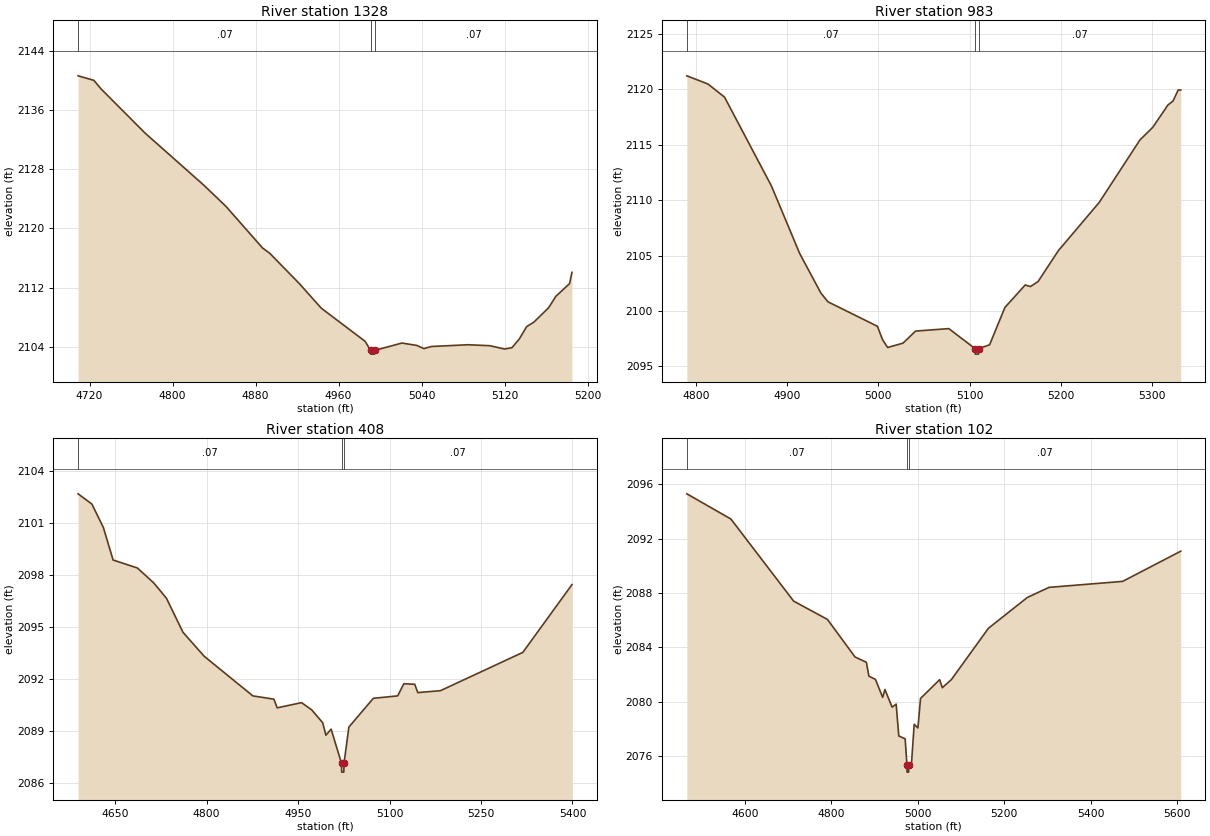
Type RM Length L Ch R = 1,1328,345,345,345
BEGIN DESCRIPTION:
Stream0124 3.0
END DESCRIPTION:
XS GIS Cut Line= 2
      1787372.98     13941561.55      1787039.82     13941901.66
#Sta/Elev= 30
  4708.9 2140.63  4724.1 2140.02  4731.1 2138.85  4773.5 2132.88  4830.1 2125.84
  4851.4 2122.98  4886.7 2117.35  4893.8 2116.61  4922.1 2112.54  4943.3 2109.21
  4985.7 2104.71  4990.8 2103.49  4991.1 2102.99  4994.6 2102.99  4994.8 2103.49
  5021.1 2104.49  5035.3 2104.17  5042.3 2103.74  5049.4 2104.02  5084.7 2104.26
  5105.8 2104.13  5120.0 2103.68  5127.1 2103.86  5134.1 2105.01  5141.3 2106.71
  5148.3 2107.32  5162.4 2109.25  5169.6 2110.83  5182.7 2112.53  5185.0 2114.05
#Mann=3,-1,0
  4708.9    0.07       0  4990.8    0.05       0  4994.8    0.07       0
Bank Sta=4990.8,4994.8
Exp/Cntr=0.3,0.1

Type RM Length L Ch R = 1,983,575,575,575
BEGIN DESCRIPTION:
Stream0124 2.0
END DESCRIPTION:
XS GIS Cut Line= 3
      1787125.05     13941474.99      1786925.00     13941525.00
      1786775.01     13941824.99
#Sta/Elev= 30
  4790.0 2121.21  4813.2 2120.47  4831.3 2119.29  4882.8 2111.27  4913.7 2105.19
  4936.9 2101.63  4944.7 2100.83  4999.0 2098.62  5004.6 2097.41  5010.2 2096.71
  5027.0 2097.10  5040.9 2098.19  5077.3 2098.41  5106.0 2096.61  5106.3 2096.11
  5109.8 2096.11  5110.0 2096.61  5122.0 2096.95  5138.8 2100.32  5161.1 2102.35
  5166.7 2102.20  5175.1 2102.65  5197.5 2105.45  5242.2 2109.79  5286.9 2115.43
  5300.9 2116.56  5317.6 2118.58  5323.2 2118.94  5328.8 2119.93  5331.6 2119.93
#Mann=3,-1,0
  4790.0    0.07       0  5106.0    0.05       0  5110.0    0.07       0
Bank Sta=5106,5110
Exp/Cntr=0.3,0.1

Type RM Length L Ch R = 1,408,306,306,306
BEGIN DESCRIPTION:
Stream0124 1.0
END DESCRIPTION:
XS GIS Cut Line= 3
      1786925.04     13941174.99      1786528.27     13941281.88
      1786505.36     13941680.31
#Sta/Elev= 30
  4589.2 2102.66  4611.8 2102.07  4630.7 2100.71  4646.6 2098.84  4686.5 2098.38
  4713.5 2097.51  4734.2 2096.63  4761.2 2094.67  4795.9 2093.29  4875.8 2091.00
  4910.3 2090.81  4915.7 2090.31  4955.7 2090.61  4972.4 2090.19  4990.4 2089.45
  4995.6 2088.73  5004.2 2089.08  5021.3 2087.10  5021.5 2086.60  5025.0 2086.60
  5025.3 2087.10  5033.3 2089.20  5073.4 2090.86  5113.4 2091.00  5123.4 2091.70
  5141.3 2091.67  5146.3 2091.19  5183.5 2091.30  5318.6 2093.51  5399.2 2097.42
#Mann=3,-1,0
  4589.2    0.07       0  5021.3    0.05       0  5025.3    0.07       0
Bank Sta=5021.3,5025.3
Exp/Cntr=0.3,0.1

Type RM Length L Ch R = 1,102,0,0,0
BEGIN DESCRIPTION:
Stream0124 0.0
END DESCRIPTION:
XS GIS Cut Line= 4
      1786849.88     13940869.46      1786396.80     13941017.02
      1786294.37     13941159.38      1786325.62     13941649.00
#Sta/Elev= 30
  4465.9 2095.30  4567.7 2093.45  4712.9 2087.41  4791.2 2086.06  4855.0 2083.30
  4881.2 2082.91  4887.0 2081.89  4902.2 2081.65  4918.9 2080.33  4924.1 2080.91
  4940.7 2079.61  4950.1 2079.83  4956.2 2077.49  4970.9 2077.28  4975.1 2075.33
  4975.4 2074.83  4978.9 2074.83  4979.1 2075.33  4985.7 2075.53  4991.8 2078.35
  5000.4 2078.08  5006.5 2080.25  5050.7 2081.63  5056.9 2081.04  5077.7 2081.63
  5163.5 2085.41  5253.7 2087.68  5303.8 2088.42  5474.1 2088.86  5608.4 2091.08
#Mann=3,-1,0
  4465.9    0.07       0  4975.1    0.05       0  4979.1    0.07       0
Bank Sta=4975.1,4979.1
Exp/Cntr=0.3,0.1

Chan Stop Cuts=-1