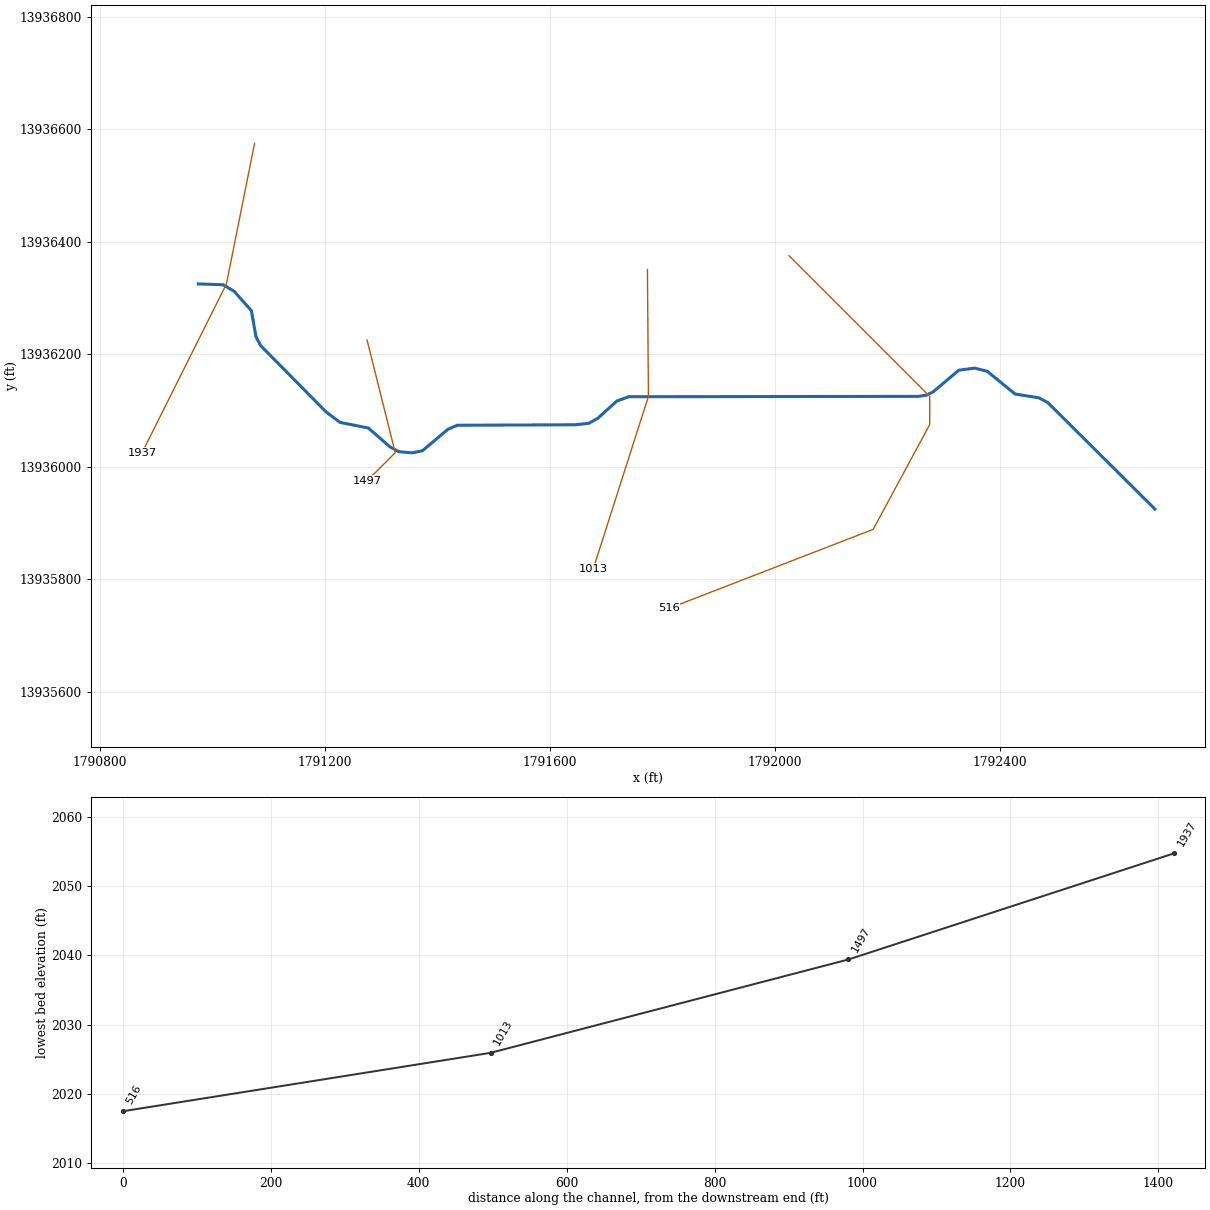
--- Stream0126.prj (project) ---

Proj Title=Stream0126 Base Level Engineering
Current Plan=p01
Default Exp/Contr=0.3,0.1
English Units
Geom File=g01
Flow File=f01
Plan File=p01
BEGIN DESCRIPTION:
Stream0126
END DESCRIPTION:

--- Stream0126.p01 (plan) ---

Plan Title=Multiple Run
Short Identifier=Multiple
Geom File=g01
Flow File=f01
Subcritical Flow
K Sum by GR= 0
Std Step Tol= 0.01
Critical Tol= 0.01
Num of Std Step Trials= 20
Max Error Tol= 0.3
Flow Tol Ratio= 0.001
Split Flow NTrial= 30
Split Flow Tol= 0.02
Split Flow Ratio= 0.02
Log Output Level= 0
Friction Slope Method= 1
Unsteady Friction Slope Method= 2
Unsteady Bridges Friction Slope Method= 1
Parabolic Critical Depth
Global Vel Dist=  1 , 1 , 1
Global Log Level= 0
CheckData=True
Encroach Param= -1, 0, 0, 0
BEGIN DESCRIPTION:
Multiple Run
END DESCRIPTION:

--- Stream0126.f01 (steady flow) ---

Flow Title=Multiple
Number of Profiles=7
Profile Names=10-year,25-year,50-year,1pct_min,100-year,1pct_plu,500-year
River Rch & RM= Stream0126,Reach-1,1937
     421     681     917     599    1195    2385    2002
Boundary for River Rch & Prof#=Stream0126,Reach-1,1
Up Type=0
Dn Type=3
Dn Slope=0.005
Boundary for River Rch & Prof#=Stream0126,Reach-1,2
Up Type=0
Dn Type=3
Dn Slope=0.005
Boundary for River Rch & Prof#=Stream0126,Reach-1,3
Up Type=0
Dn Type=3
Dn Slope=0.005
Boundary for River Rch & Prof#=Stream0126,Reach-1,4
Up Type=0
Dn Type=3
Dn Slope=0.005
Boundary for River Rch & Prof#=Stream0126,Reach-1,5
Up Type=0
Dn Type=3
Dn Slope=0.005
Boundary for River Rch & Prof#=Stream0126,Reach-1,6
Up Type=0
Dn Type=3
Dn Slope=0.005
Boundary for River Rch & Prof#=Stream0126,Reach-1,7
Up Type=0
Dn Type=3
Dn Slope=0.005

--- Stream0126.g01 (geometry) ---

Geom Title=Existing Conditions

River Reach=Stream0126,Reach-1
Reach XY= 30
      1790975.00     13936325.00      1791019.13     13936323.44
      1791038.78     13936311.73      1791069.29     13936277.51
      1791077.51     13936231.06      1791085.77     13936215.33
      1791201.53     13936098.01      1791226.63     13936078.94
      1791277.19     13936068.82      1791315.45     13936035.51
      1791331.11     13936026.80      1791354.82     13936024.71
      1791373.26     13936028.37      1791418.92     13936066.81
      1791435.50     13936073.76      1791645.15     13936074.64
      1791669.06     13936077.26      1791684.65     13936085.85
      1791718.94     13936116.86      1791740.22     13936124.48
      1792254.97     13936125.09      1792269.07     13936127.29
      1792281.08     13936133.19      1792326.74     13936171.63
      1792354.83     13936175.30      1792377.20     13936169.66
      1792426.74     13936129.25      1792468.97     13936122.51
      1792484.68     13936114.24      1792675.00     13935925.00

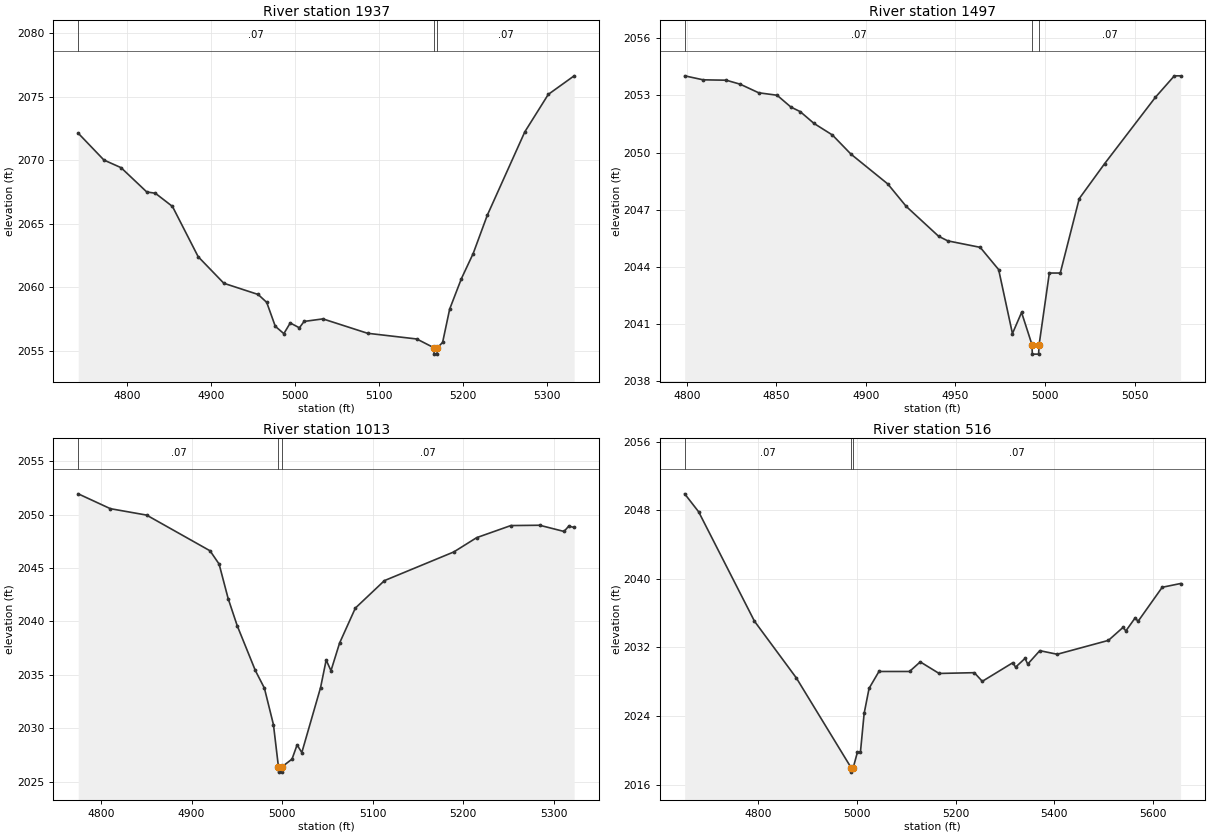
Type RM Length L Ch R = 1,1937,440,440,440
BEGIN DESCRIPTION:
Stream0126 4.0
END DESCRIPTION:
XS GIS Cut Line= 3
      1791075.00     13936575.01      1791025.00     13936325.00
      1790874.99     13936024.97
#Sta/Elev= 30
  4741.7 2072.13  4772.3 2070.02  4792.7 2069.42  4823.3 2067.51  4833.5 2067.41
  4853.9 2066.37  4884.5 2062.42  4915.1 2060.33  4955.9 2059.45  4966.1 2058.83
  4976.3 2056.95  4986.5 2056.37  4994.1 2057.21  5005.0 2056.83  5010.6 2057.33
  5033.0 2057.53  5086.1 2056.40  5144.8 2055.95  5165.2 2055.26  5165.4 2054.76
  5168.9 2054.76  5169.2 2055.26  5175.5 2055.68  5183.9 2058.30  5197.9 2060.70
  5211.9 2062.67  5228.7 2065.68  5273.4 2072.24  5301.3 2075.18  5332.1 2076.64
#Mann=3,-1,0
  4741.7    0.07       0  5165.2    0.05       0  5169.2    0.07       0
Bank Sta=5165.2,5169.2
Exp/Cntr=0.3,0.1

Type RM Length L Ch R = 1,1497,484,484,484
BEGIN DESCRIPTION:
Stream0126 3.0
END DESCRIPTION:
XS GIS Cut Line= 3
      1791274.99     13936225.03      1791325.00     13936025.00
      1791275.00     13935975.00
#Sta/Elev= 30
  4798.8 2054.03  4809.1 2053.82  4822.0 2053.80  4829.8 2053.59  4840.1 2053.14
  4850.4 2053.01  4858.1 2052.39  4863.3 2052.15  4871.0 2051.53  4881.3 2050.92
  4891.6 2049.92  4912.2 2048.35  4922.5 2047.17  4940.6 2045.60  4945.7 2045.36
  4963.8 2045.02  4974.1 2043.85  4981.8 2040.49  4986.9 2041.60  4992.7 2039.91
  4992.9 2039.41  4996.4 2039.41  4996.7 2039.91  5002.4 2043.67  5008.5 2043.67
  5019.1 2047.58  5033.3 2049.42  5061.6 2052.90  5072.2 2054.03  5075.7 2054.03
#Mann=3,-1,0
  4798.8    0.07       0  4992.7    0.05       0  4996.7    0.07       0
Bank Sta=4992.7,4996.7
Exp/Cntr=0.3,0.1

Type RM Length L Ch R = 1,1013,497,497,497
BEGIN DESCRIPTION:
Stream0126 2.0
END DESCRIPTION:
XS GIS Cut Line= 3
      1791773.25     13936350.47      1791775.00     13936125.00
      1791676.91     13935818.39
#Sta/Elev= 30
  4774.9 2051.94  4810.4 2050.55  4850.4 2049.95  4920.4 2046.61  4930.4 2045.37
  4940.4 2042.14  4950.4 2039.60  4970.4 2035.41  4980.4 2033.76  4990.4 2030.34
  4995.9 2026.40  4996.1 2025.90  4999.6 2025.90  4999.9 2026.40  5010.9 2027.12
  5016.5 2028.45  5021.7 2027.73  5042.4 2033.81  5048.6 2036.39  5053.9 2035.39
  5063.4 2037.98  5080.8 2041.25  5112.9 2043.82  5189.4 2046.50  5214.7 2047.84
  5252.4 2048.97  5284.2 2049.00  5311.1 2048.42  5316.4 2048.92  5322.3 2048.79
#Mann=3,-1,0
  4774.9    0.07       0  4995.9    0.05       0  4999.9    0.07       0
Bank Sta=4995.9,4999.9
Exp/Cntr=0.3,0.1

Type RM Length L Ch R = 1,516,0,0,0
BEGIN DESCRIPTION:
Stream0126 1.0
END DESCRIPTION:
XS GIS Cut Line= 5
      1792024.99     13936375.01      1792275.00     13936125.00
      1792275.00     13936075.00      1792174.51     13935888.75
      1791811.17     13935748.12
#Sta/Elev= 30
  4651.0 2049.94  4679.3 2047.84  4792.4 2035.07  4877.3 2028.44  4988.4 2017.95
  4988.7 2017.45  4992.4 2017.95  5001.0 2019.78  5007.1 2019.78  5014.6 2024.30
  5024.6 2027.23  5044.6 2029.20  5106.5 2029.20  5128.3 2030.32  5166.5 2028.97
  5237.8 2029.06  5254.0 2028.05  5316.0 2030.23  5321.4 2029.70  5340.6 2030.73
  5346.0 2030.06  5370.5 2031.63  5405.8 2031.21  5509.5 2032.83  5539.4 2034.36
  5544.8 2033.93  5564.0 2035.48  5569.4 2035.04  5618.5 2039.03  5655.8 2039.47
#Mann=3,-1,0
  4651.0    0.07       0  4988.4    0.05       0  4992.4    0.07       0
Bank Sta=4988.4,4992.4
Exp/Cntr=0.3,0.1

Chan Stop Cuts=-1