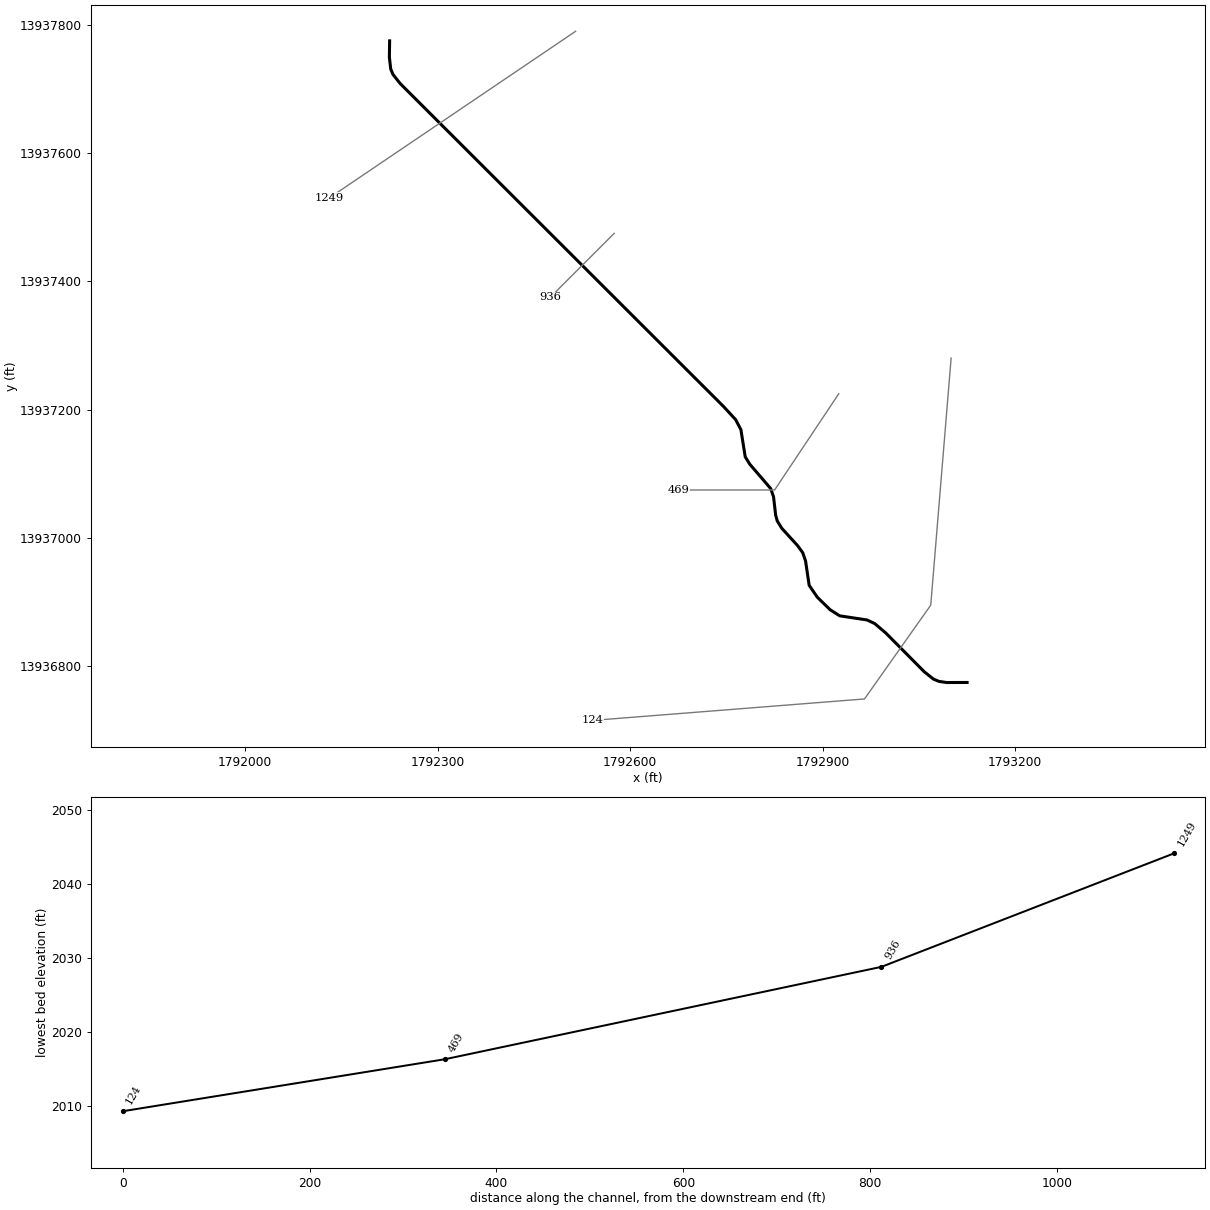
--- Stream0127.prj (project) ---

Proj Title=Stream0127 Base Level Engineering
Current Plan=p01
Default Exp/Contr=0.3,0.1
English Units
Geom File=g01
Flow File=f01
Plan File=p01
BEGIN DESCRIPTION:
Stream0127
END DESCRIPTION:

--- Stream0127.p01 (plan) ---

Plan Title=Multiple Run
Short Identifier=Multiple
Geom File=g01
Flow File=f01
Subcritical Flow
K Sum by GR= 0
Std Step Tol= 0.01
Critical Tol= 0.01
Num of Std Step Trials= 20
Max Error Tol= 0.3
Flow Tol Ratio= 0.001
Split Flow NTrial= 30
Split Flow Tol= 0.02
Split Flow Ratio= 0.02
Log Output Level= 0
Friction Slope Method= 1
Unsteady Friction Slope Method= 2
Unsteady Bridges Friction Slope Method= 1
Parabolic Critical Depth
Global Vel Dist=  1 , 1 , 1
Global Log Level= 0
CheckData=True
Encroach Param= -1, 0, 0, 0
BEGIN DESCRIPTION:
Multiple Run
END DESCRIPTION:

--- Stream0127.f01 (steady flow) ---

Flow Title=Multiple
Number of Profiles=7
Profile Names=10-year,25-year,50-year,1pct_min,100-year,1pct_plu,500-year
River Rch & RM= Stream0127,Reach-1,1249
     329     525     700     453     905    1805    1489
Boundary for River Rch & Prof#=Stream0127,Reach-1,1
Up Type=0
Dn Type=3
Dn Slope=0.005
Boundary for River Rch & Prof#=Stream0127,Reach-1,2
Up Type=0
Dn Type=3
Dn Slope=0.005
Boundary for River Rch & Prof#=Stream0127,Reach-1,3
Up Type=0
Dn Type=3
Dn Slope=0.005
Boundary for River Rch & Prof#=Stream0127,Reach-1,4
Up Type=0
Dn Type=3
Dn Slope=0.005
Boundary for River Rch & Prof#=Stream0127,Reach-1,5
Up Type=0
Dn Type=3
Dn Slope=0.005
Boundary for River Rch & Prof#=Stream0127,Reach-1,6
Up Type=0
Dn Type=3
Dn Slope=0.005
Boundary for River Rch & Prof#=Stream0127,Reach-1,7
Up Type=0
Dn Type=3
Dn Slope=0.005

--- Stream0127.g01 (geometry) ---

Geom Title=Existing Conditions

River Reach=Stream0127,Reach-1
Reach XY= 30
      1792225.00     13937775.00      1792224.59     13937749.63
      1792226.68     13937731.14      1792230.31     13937722.48
      1792241.58     13937708.30      1792745.39     13937205.16
      1792764.24     13937184.68      1792772.50     13937168.97
      1792779.19     13937126.74      1792786.10     13937115.46
      1792818.92     13937077.20      1792823.35     13937064.31
      1792826.65     13937035.68      1792829.16     13937026.72
      1792836.08     13937015.45      1792861.01     13936988.05
      1792868.89     13936977.16      1792873.28     13936964.25
      1792878.86     13936926.42      1792891.49     13936907.95
      1792911.44     13936888.48      1792926.43     13936878.88
      1792968.91     13936872.45      1792981.03     13936866.83
      1792998.45     13936851.96      1793058.31     13936791.62
      1793072.49     13936780.33      1793081.15     13936776.69
      1793093.12     13936774.93      1793125.00     13936775.00

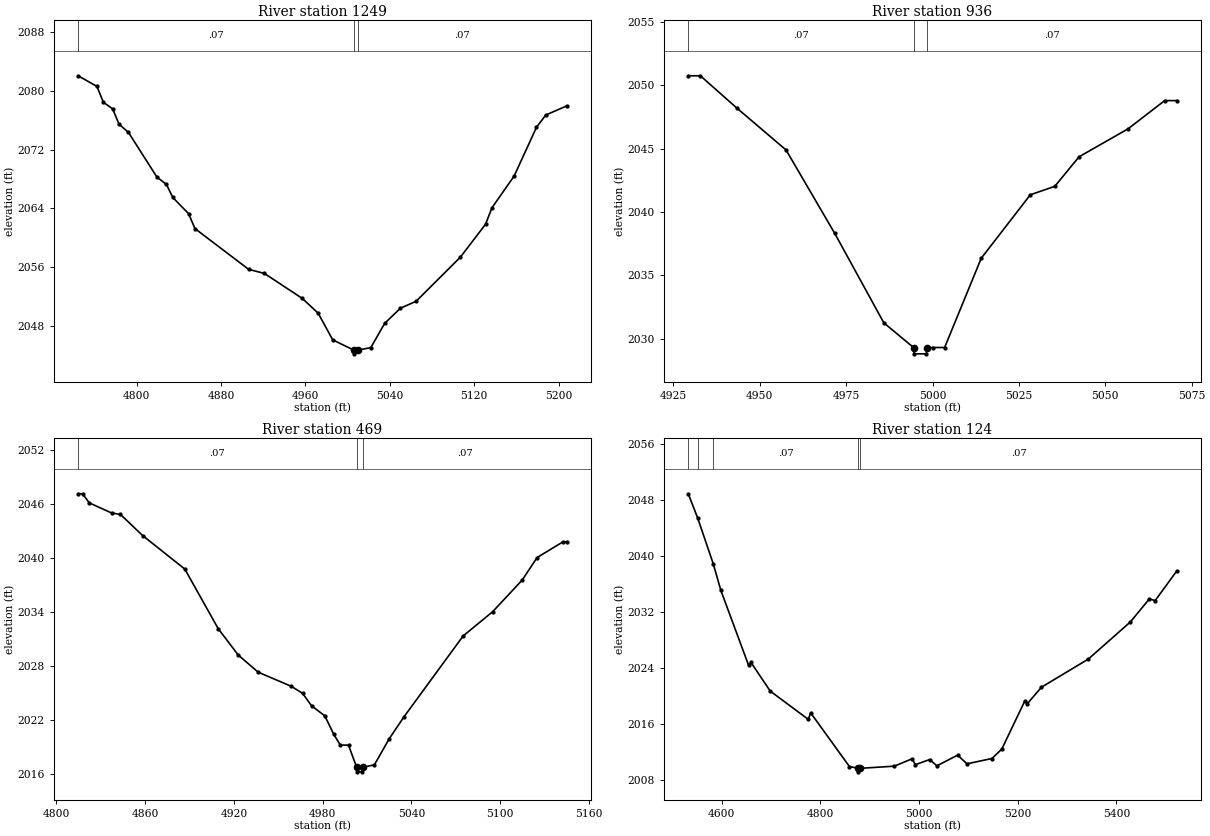
Type RM Length L Ch R = 1,1249,313,313,313
BEGIN DESCRIPTION:
Stream0127 3.0
END DESCRIPTION:
XS GIS Cut Line= 2
      1792514.82     13937789.90      1792131.27     13937530.39
#Sta/Elev= 30
  4744.5 2082.07  4762.3 2080.62  4768.4 2078.46  4777.2 2077.56  4783.3 2075.46
  4792.2 2074.35  4819.2 2068.25  4828.2 2067.26  4834.2 2065.48  4849.2 2063.27
  4855.2 2061.24  4906.1 2055.68  4921.1 2055.12  4957.0 2051.71  4972.0 2049.71
  4985.8 2046.07  5005.9 2044.66  5006.2 2044.16  5009.9 2044.66  5022.0 2045.02
  5035.0 2048.30  5049.9 2050.37  5064.9 2051.33  5106.9 2057.35  5130.7 2061.83
  5136.8 2064.08  5157.8 2068.40  5178.9 2075.02  5187.7 2076.71  5207.6 2077.96
#Mann=3,-1,0
  4744.5    0.07       0  5005.9    0.05       0  5009.9    0.07       0
Bank Sta=5005.9,5009.9
Exp/Cntr=0.3,0.1

Type RM Length L Ch R = 1,936,467,467,467
BEGIN DESCRIPTION:
Stream0127 2.0
END DESCRIPTION:
XS GIS Cut Line= 3
      1792574.99     13937474.99      1792525.00     13937425.00
      1792475.01     13937375.01
#Sta/Elev= 19
  4929.3 2050.75  4932.8 2050.75  4943.4 2048.19  4957.6 2044.89  4971.7 2038.30
  4985.9 2031.24  4994.5 2029.29  4994.7 2028.79  4998.2 2028.79  4998.5 2029.29
  5000.0 2029.29  5003.5 2029.29  5014.1 2036.34  5028.3 2041.35  5035.4 2042.02
  5042.4 2044.35  5056.6 2046.56  5067.2 2048.79  5070.7 2048.79
#Mann=3,-1,0
  4929.3    0.07       0  4994.5    0.05       0  4998.5    0.07       0
Bank Sta=4994.5,4998.5
Exp/Cntr=0.3,0.1

Type RM Length L Ch R = 1,469,345,345,345
BEGIN DESCRIPTION:
Stream0127 1.0
END DESCRIPTION:
XS GIS Cut Line= 3
      1792925.01     13937225.01      1792825.00     13937075.00
      1792675.00     13937075.00
#Sta/Elev= 30
  4814.7 2047.16  4817.7 2047.16  4822.2 2046.15  4837.3 2045.03  4843.3 2044.87
  4858.3 2042.52  4886.8 2038.80  4909.4 2032.18  4922.9 2029.26  4936.4 2027.35
  4958.9 2025.77  4966.5 2024.99  4972.5 2023.62  4981.5 2022.49  4987.5 2020.45
  4992.0 2019.25  4997.5 2019.25  5003.0 2016.78  5003.2 2016.28  5006.7 2016.28
  5007.0 2016.78  5015.0 2017.06  5025.0 2019.95  5035.0 2022.39  5075.0 2031.37
  5095.0 2034.07  5115.0 2037.59  5125.0 2040.08  5142.5 2041.82  5145.0 2041.82
#Mann=3,-1,0
  4814.7    0.07       0  5003.0    0.05       0  5007.0    0.07       0
Bank Sta=5003,5007
Exp/Cntr=0.3,0.1

Type RM Length L Ch R = 1,124,0,0,0
BEGIN DESCRIPTION:
Stream0127 0.0
END DESCRIPTION:
XS GIS Cut Line= 4
      1793100.14     13937280.63      1793068.37     13936895.52
      1792965.10     13936749.32      1792541.33     13936715.87
#Sta/Elev= 30
  4532.0 2048.84  4551.3 2045.34  4582.8 2038.83  4597.9 2035.11  4654.2 2024.42
  4659.2 2024.81  4698.2 2020.73  4775.2 2016.71  4780.2 2017.63  4858.7 2009.99
  4876.8 2009.73  4877.1 2009.23  4880.8 2009.73  4950.0 2010.04  4985.7 2011.09
  4992.5 2010.25  5021.4 2010.98  5036.1 2010.09  5078.2 2011.61  5097.0 2010.37
  5147.7 2011.13  5167.7 2012.47  5214.4 2019.34  5219.4 2018.93  5248.0 2021.28
  5343.1 2025.29  5428.5 2030.59  5466.8 2033.86  5478.7 2033.63  5522.5 2037.85
#Mann=5,-1,0
  4532.0    0.07       0  4551.3   0.035       0  4582.8    0.07       0
  4876.8    0.05       0  4880.8    0.07       0
Bank Sta=4876.8,4880.8
Exp/Cntr=0.3,0.1

Chan Stop Cuts=-1