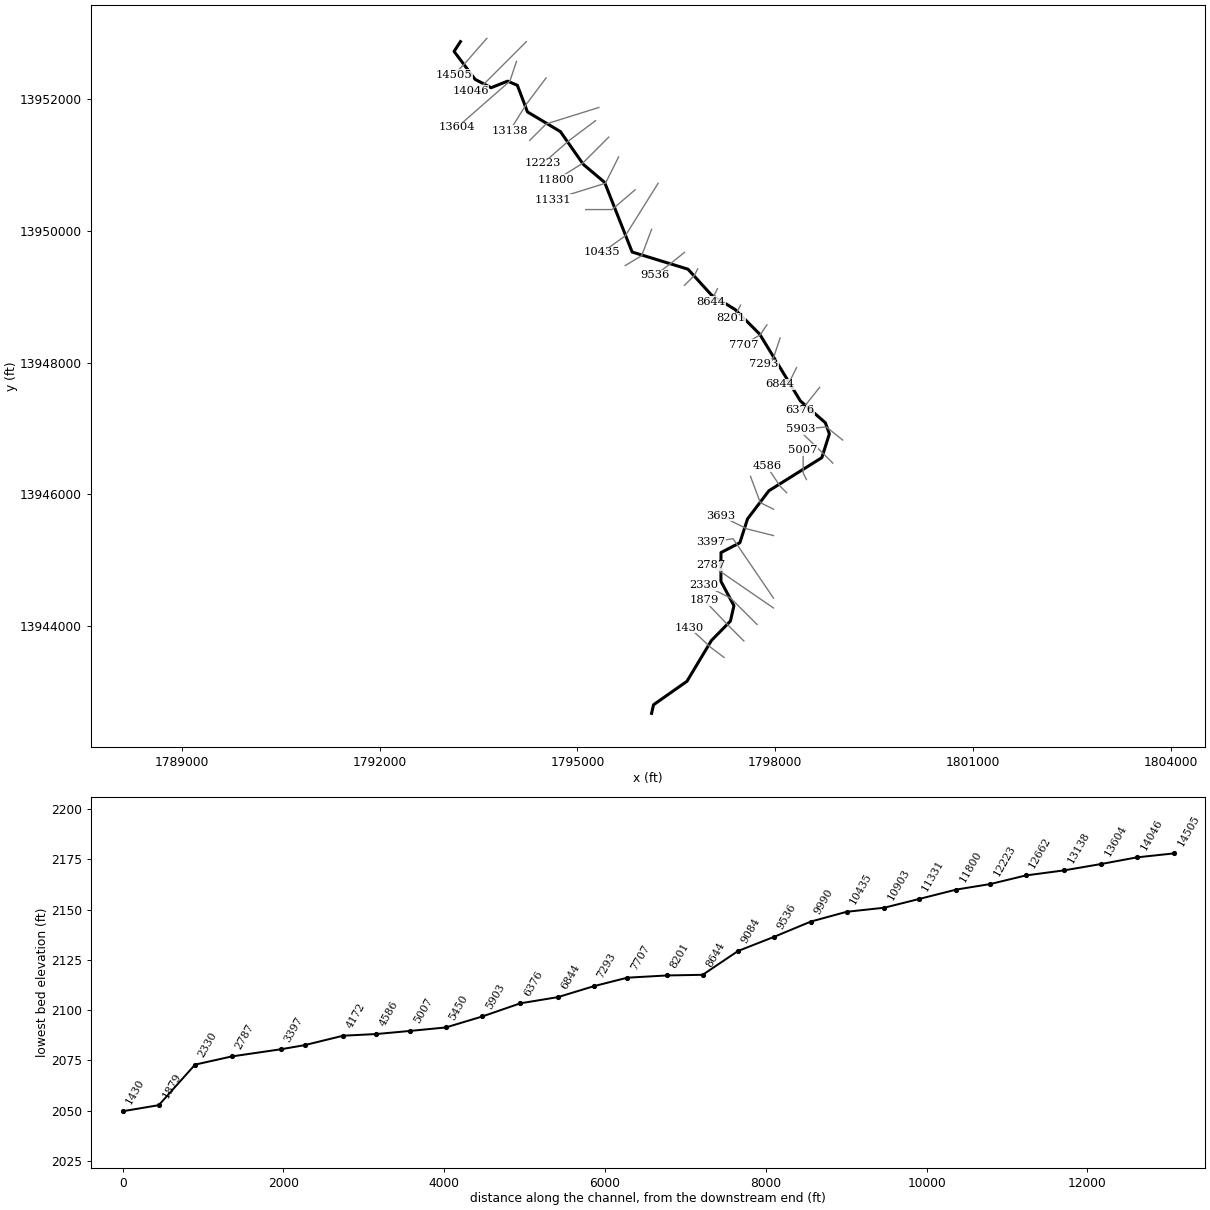
--- Stream0128.prj (project) ---

Proj Title=Stream0128 Base Level Engineering
Current Plan=p01
Default Exp/Contr=0.3,0.1
English Units
Geom File=g01
Flow File=f01
Plan File=p01
BEGIN DESCRIPTION:
Stream0128
END DESCRIPTION:

--- Stream0128.p01 (plan) ---

Plan Title=Multiple Run
Short Identifier=Multiple
Geom File=g01
Flow File=f01
Subcritical Flow
K Sum by GR= 0
Std Step Tol= 0.01
Critical Tol= 0.01
Num of Std Step Trials= 20
Max Error Tol= 0.3
Flow Tol Ratio= 0.001
Split Flow NTrial= 30
Split Flow Tol= 0.02
Split Flow Ratio= 0.02
Log Output Level= 0
Friction Slope Method= 1
Unsteady Friction Slope Method= 2
Unsteady Bridges Friction Slope Method= 1
Parabolic Critical Depth
Global Vel Dist=  1 , 1 , 1
Global Log Level= 0
CheckData=True
Encroach Param= -1, 0, 0, 0
BEGIN DESCRIPTION:
Multiple Run
END DESCRIPTION:

--- Stream0128.f01 (steady flow) ---

Flow Title=Multiple
Number of Profiles=7
Profile Names=10-year,25-year,50-year,1pct_min,100-year,1pct_plu,500-year
River Rch & RM= Stream0128,Reach-1,14505
    1623    2819    3971    2695    5376   10727    9758
River Rch & RM= Stream0128,Reach-1,6844
    2095    3688    5243    3588    7159   14284   13219
River Rch & RM= Stream0128,Reach-1,5450
    2591    4610    6599    4546    9070   18097   16967
Boundary for River Rch & Prof#=Stream0128,Reach-1,1
Up Type=0
Dn Type=3
Dn Slope=0.005
Boundary for River Rch & Prof#=Stream0128,Reach-1,2
Up Type=0
Dn Type=3
Dn Slope=0.005
Boundary for River Rch & Prof#=Stream0128,Reach-1,3
Up Type=0
Dn Type=3
Dn Slope=0.005
Boundary for River Rch & Prof#=Stream0128,Reach-1,4
Up Type=0
Dn Type=3
Dn Slope=0.005
Boundary for River Rch & Prof#=Stream0128,Reach-1,5
Up Type=0
Dn Type=3
Dn Slope=0.005
Boundary for River Rch & Prof#=Stream0128,Reach-1,6
Up Type=0
Dn Type=3
Dn Slope=0.005
Boundary for River Rch & Prof#=Stream0128,Reach-1,7
Up Type=0
Dn Type=3
Dn Slope=0.005

--- Stream0128.g01 (geometry) ---

Geom Title=Existing Conditions

River Reach=Stream0128,Reach-1
Reach XY= 30
      1793225.00     13952875.00      1793128.10     13952726.65
      1793448.12     13952301.27      1793690.27     13952175.37
      1793940.39     13952274.93      1794088.57     13952211.53
      1794241.42     13951808.20      1794741.67     13951508.35
      1795088.40     13951011.70      1795411.77     13950738.67
      1795830.11     13949680.11      1796677.43     13949419.48
      1797030.61     13949030.59      1797395.09     13948805.21
      1797764.24     13948434.68      1798383.04     13947418.67
      1798761.60     13947088.30      1798822.75     13946919.06
      1798708.54     13946558.25      1797904.91     13946055.22
      1797580.47     13945627.45      1797464.24     13945265.27
      1797178.07     13945116.70      1797177.06     13944680.85
      1797374.62     13944309.73      1797321.39     13944076.50
      1797032.86     13943781.17      1796661.37     13943161.79
      1796154.43     13942805.45      1796125.00     13942675.00

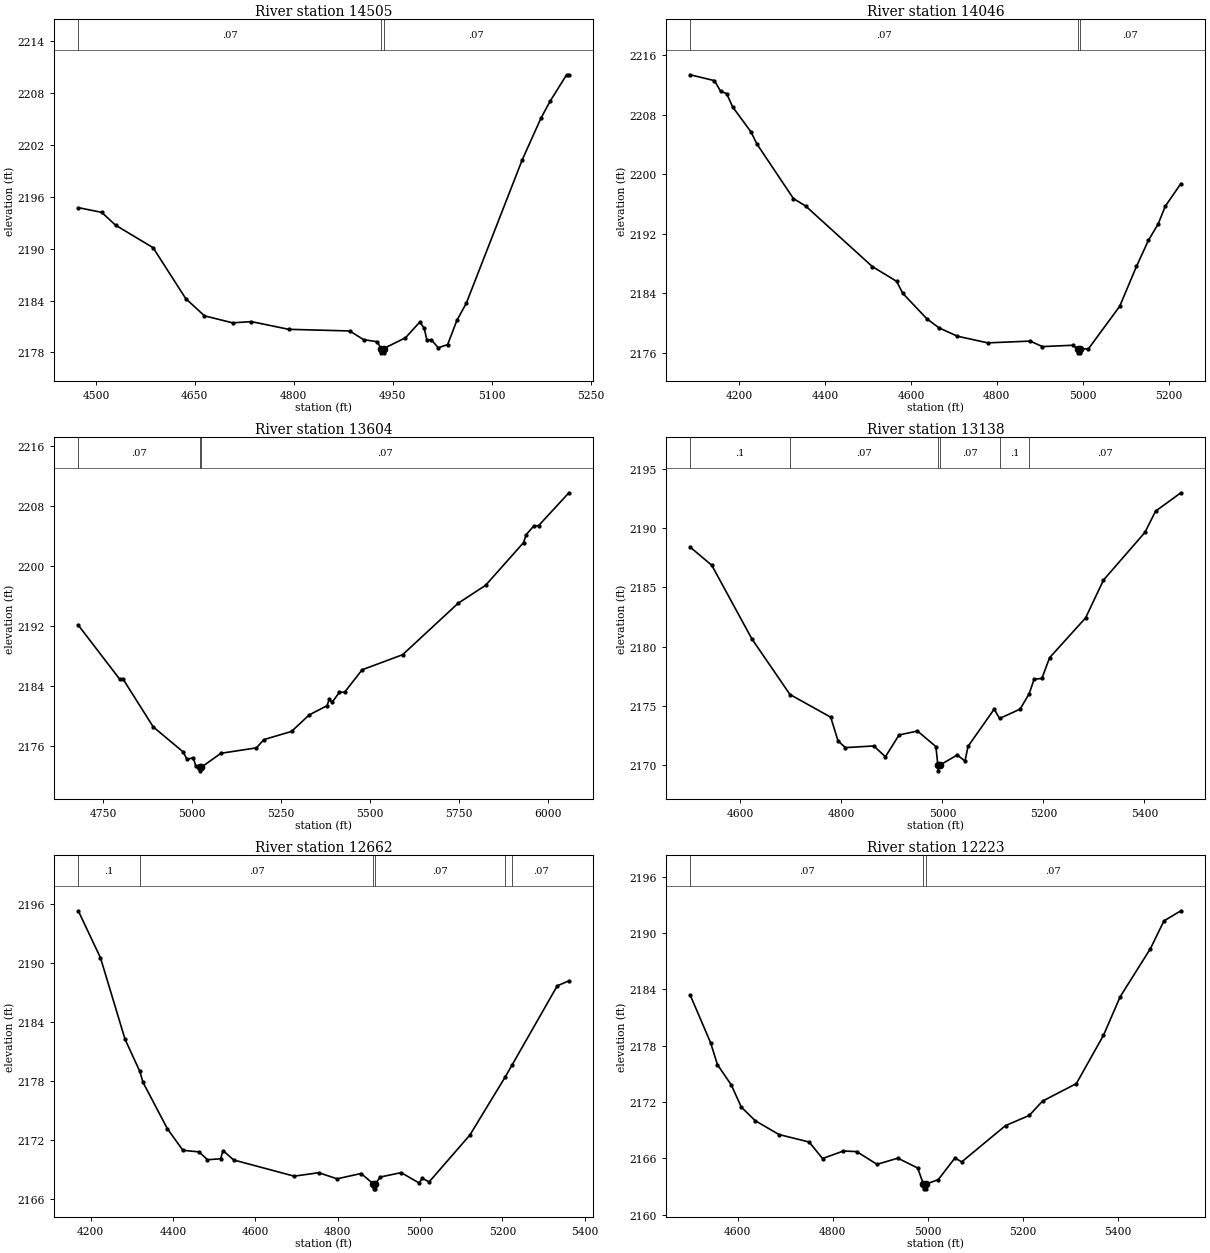
Type RM Length L Ch R = 1,14505,459,459,459
BEGIN DESCRIPTION:
Stream0128 32.0
END DESCRIPTION:
XS GIS Cut Line= 3
      1793624.99     13952924.99      1793275.00     13952525.00
      1793125.02     13952375.02
#Sta/Elev= 30
  4473.3 2194.75  4508.9 2194.20  4529.8 2192.72  4586.7 2190.12  4636.1 2184.24
  4664.5 2182.24  4707.2 2181.43  4735.7 2181.57  4792.2 2180.68  4884.7 2180.49
  4905.6 2179.49  4926.5 2179.24  4931.9 2178.46  4932.2 2177.96  4935.9 2177.96
  4936.2 2178.46  4969.2 2179.70  4991.0 2181.53  4997.7 2180.78  5001.5 2179.47
  5008.3 2179.47  5018.9 2178.55  5033.1 2178.91  5047.2 2181.73  5061.4 2183.70
  5146.2 2200.29  5174.5 2205.09  5188.6 2207.08  5213.4 2210.11  5216.9 2210.11
#Mann=3,-1,0
  4473.3    0.07       0  4931.9    0.05       0  4936.2    0.07       0
Bank Sta=4931.9,4936.2
Exp/Cntr=0.3,0.1

Type RM Length L Ch R = 1,14046,442,442,442
BEGIN DESCRIPTION:
Stream0128 31.0
END DESCRIPTION:
XS GIS Cut Line= 3
      1794224.98     13952874.98      1793575.00     13952225.00
      1793375.01     13952125.01
#Sta/Elev= 30
  4085.8 2213.39  4142.3 2212.60  4156.5 2211.17  4170.6 2210.86  4184.8 2209.05
  4227.2 2205.72  4241.3 2204.07  4326.2 2196.74  4354.5 2195.75  4510.0 2187.60
  4566.6 2185.61  4580.7 2184.01  4637.3 2180.56  4665.6 2179.35  4708.0 2178.24
  4778.7 2177.34  4877.7 2177.58  4906.0 2176.84  4976.7 2177.02  4988.7 2176.50
  4989.0 2176.00  4992.7 2176.00  4993.0 2176.50  5013.4 2176.55  5086.1 2182.26
  5125.2 2187.63  5153.1 2191.14  5175.5 2193.30  5192.3 2195.71  5228.6 2198.76
#Mann=3,-1,0
  4085.8    0.07       0  4988.7    0.05       0  4993.0    0.07       0
Bank Sta=4988.7,4993
Exp/Cntr=0.3,0.1

Type RM Length L Ch R = 1,13604,466,466,466
BEGIN DESCRIPTION:
Stream0128 30.0
END DESCRIPTION:
XS GIS Cut Line= 3
      1794075.00     13952575.00      1793975.00     13952275.00
      1793175.03     13951575.03
#Sta/Elev= 30
  4679.5 2192.12  4795.5 2184.95  4806.0 2184.89  4890.3 2178.56  4974.6 2175.22
  4985.2 2174.23  5002.8 2174.46  5009.5 2173.40  5021.5 2173.21  5021.8 2172.71
  5025.9 2173.21  5080.7 2175.05  5180.3 2175.77  5201.2 2176.87  5279.0 2177.96
  5328.4 2180.15  5378.7 2181.39  5385.3 2182.27  5392.9 2181.82  5413.8 2183.20
  5428.1 2183.18  5477.4 2186.17  5591.3 2188.18  5747.0 2195.02  5824.8 2197.44
  5931.1 2203.11  5938.7 2204.18  5959.6 2205.31  5973.8 2205.39  6058.7 2209.75
#Mann=3,-1,0
  4679.5    0.07       0  5021.5    0.05       0  5025.9    0.07       0
Bank Sta=5021.5,5025.9
Exp/Cntr=0.3,0.1

Type RM Length L Ch R = 1,13138,476,476,476
BEGIN DESCRIPTION:
Stream0128 29.0
END DESCRIPTION:
XS GIS Cut Line= 3
      1794525.02     13952325.02      1794225.00     13951925.00
      1793975.01     13951525.02
#Sta/Elev= 30
  4500.5 2188.40  4543.2 2186.87  4622.4 2180.67  4698.1 2175.96  4778.7 2174.05
  4793.2 2172.05  4807.8 2171.48  4864.1 2171.62  4887.0 2170.71  4914.1 2172.55
  4950.5 2172.88  4987.0 2171.57  4990.9 2170.02  4991.2 2169.52  4995.5 2170.02
  5029.4 2170.86  5044.7 2170.34  5050.6 2171.58  5102.5 2174.73  5113.1 2173.94
  5153.8 2174.73  5171.8 2176.03  5181.5 2177.25  5196.9 2177.32  5212.2 2179.07
  5283.5 2182.43  5318.9 2185.62  5400.9 2189.64  5422.1 2191.44  5472.2 2192.99
#Mann=6,-1,0
  4500.5     0.1       0  4698.1    0.07       0  4990.9    0.05       0
  4995.5    0.07       0  5113.1     0.1       0  5171.8    0.07       0
Bank Sta=4990.9,4995.5
Exp/Cntr=0.3,0.1

Type RM Length L Ch R = 1,12662,439,439,439
BEGIN DESCRIPTION:
Stream0128 28.0
END DESCRIPTION:
XS GIS Cut Line= 3
      1795325.03     13951875.01      1794525.00     13951625.00
      1794275.03     13951375.03
#Sta/Elev= 30
  4169.8 2195.28  4223.8 2190.49  4283.5 2182.20  4319.3 2178.94  4327.0 2177.83
  4386.2 2173.11  4423.9 2170.91  4463.2 2170.75  4483.6 2169.95  4515.6 2170.05
  4521.3 2170.89  4547.0 2169.93  4694.2 2168.28  4753.9 2168.63  4798.4 2168.01
  4856.6 2168.55  4886.7 2167.49  4887.1 2166.99  4891.1 2166.99  4891.4 2167.49
  4903.2 2168.19  4954.0 2168.64  4997.5 2167.59  5005.4 2168.06  5022.1 2167.70
  5121.1 2172.47  5207.0 2178.39  5223.7 2179.61  5333.3 2187.65  5361.5 2188.15
#Mann=6,-1,0
  4169.8     0.1       0  4319.3    0.07       0  4886.7    0.05       0
  4891.4    0.07       0  5207.0     0.1       0  5223.7    0.07       0
Bank Sta=4886.7,4891.4
Exp/Cntr=0.3,0.1

Type RM Length L Ch R = 1,12223,423,423,423
BEGIN DESCRIPTION:
Stream0128 27.0
END DESCRIPTION:
XS GIS Cut Line= 3
      1795275.02     13951675.02      1794875.00     13951375.00
      1794475.03     13951025.02
#Sta/Elev= 30
  4500.2 2183.39  4542.9 2178.33  4557.5 2175.97  4586.7 2173.80  4607.5 2171.46
  4636.7 2170.01  4686.7 2168.53  4750.2 2167.73  4778.4 2165.97  4822.1 2166.77
  4850.2 2166.71  4892.9 2165.35  4936.7 2166.01  4978.4 2164.96  4990.4 2163.24
  4990.8 2162.74  4995.1 2162.74  4995.5 2163.24  5021.6 2163.72  5056.7 2166.03
  5070.9 2165.61  5163.0 2169.48  5212.8 2170.56  5240.8 2172.09  5312.0 2173.96
  5369.0 2179.11  5404.1 2183.22  5467.7 2188.35  5496.1 2191.30  5531.7 2192.38
#Mann=3,-1,0
  4500.2    0.07       0  4990.4    0.05       0  4995.5    0.07       0
Bank Sta=4990.4,4995.5
Exp/Cntr=0.3,0.1

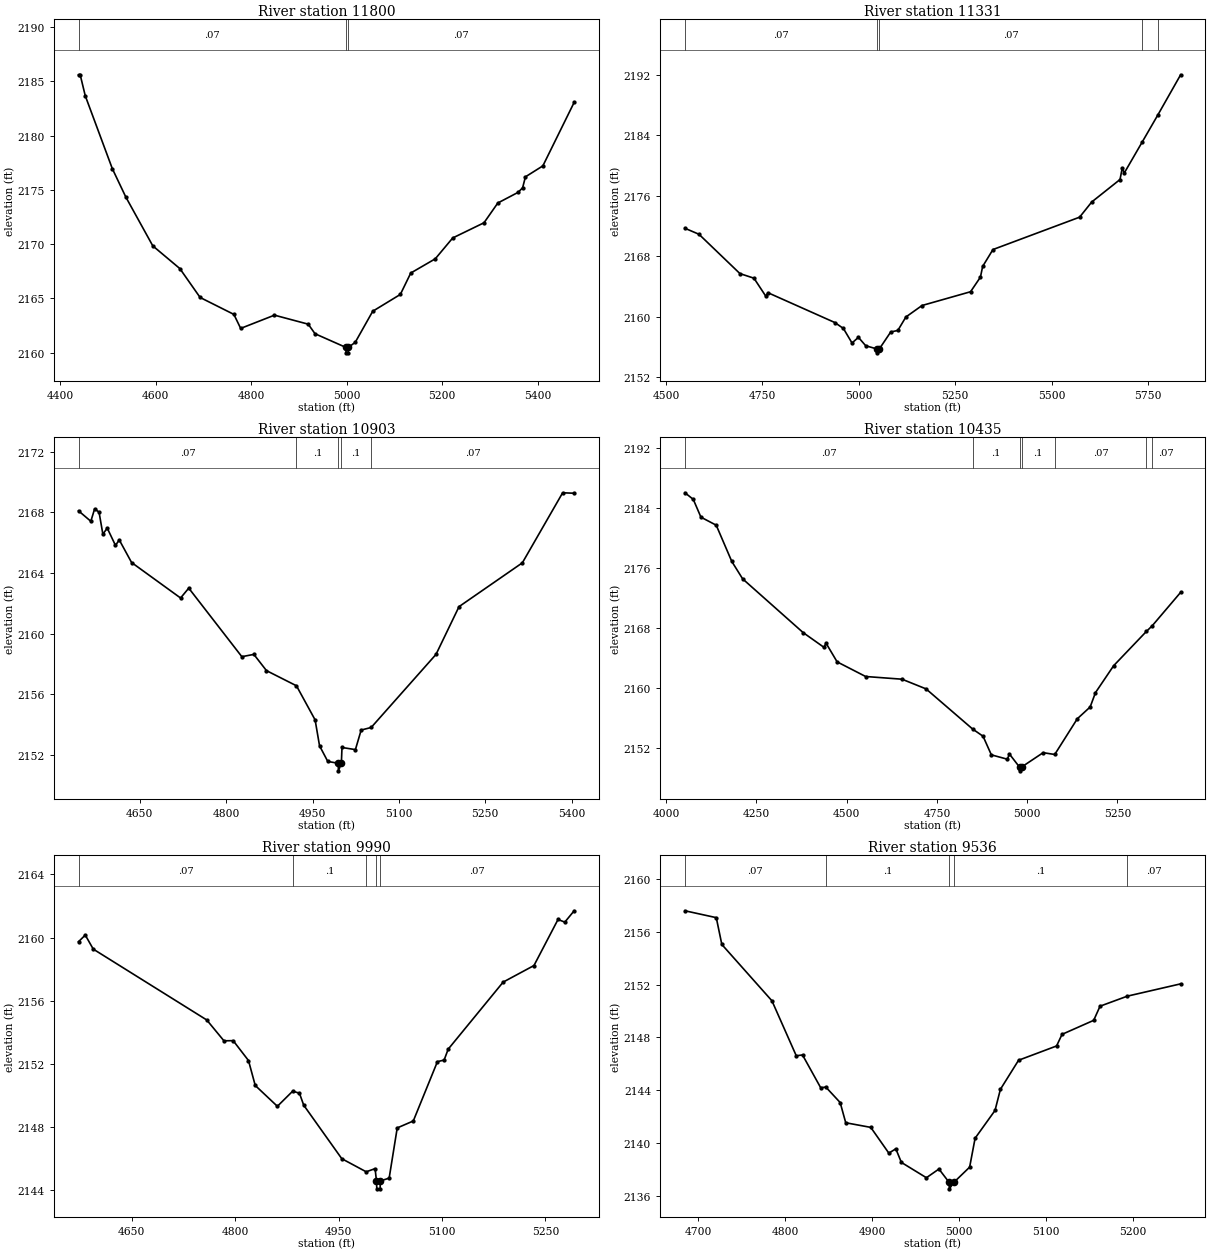
Type RM Length L Ch R = 1,11800,469,469,469
BEGIN DESCRIPTION:
Stream0128 26.0
END DESCRIPTION:
XS GIS Cut Line= 3
      1795474.99     13951424.99      1795075.00     13951025.00
      1794674.97     13950774.98
#Sta/Elev= 30
  4438.7 2185.60  4442.2 2185.60  4452.8 2183.67  4509.4 2176.96  4537.7 2174.34
  4594.2 2169.84  4650.8 2167.75  4693.2 2165.09  4763.9 2163.53  4778.1 2162.24
  4848.8 2163.46  4919.5 2162.63  4933.7 2161.75  4998.3 2160.49  4998.7 2159.99
  5003.0 2159.99  5003.4 2160.49  5017.9 2160.96  5054.5 2163.82  5112.3 2165.37
  5134.1 2167.34  5185.4 2168.65  5221.9 2170.57  5287.4 2171.97  5316.3 2173.79
  5358.7 2174.77  5368.2 2175.19  5374.1 2176.20  5410.6 2177.21  5476.1 2183.06
#Mann=3,-1,0
  4438.7    0.07       0  4998.3    0.05       0  5003.4    0.07       0
Bank Sta=4998.3,5003.4
Exp/Cntr=0.3,0.1

Type RM Length L Ch R = 1,11331,428,428,428
BEGIN DESCRIPTION:
Stream0128 25.0
END DESCRIPTION:
XS GIS Cut Line= 3
      1795625.00     13951124.99      1795425.00     13950725.00
      1794624.96     13950474.99
#Sta/Elev= 30
  4549.1 2171.72  4585.4 2170.93  4691.6 2165.73  4728.0 2165.12  4758.7 2162.74
  4764.3 2163.20  4937.6 2159.26  4960.0 2158.47  4982.3 2156.55  4998.9 2157.30
  5017.8 2156.19  5047.7 2155.75  5048.1 2155.25  5052.9 2155.75  5082.7 2158.01
  5101.1 2158.21  5122.0 2159.99  5163.9 2161.51  5289.7 2163.33  5315.3 2165.26
  5321.1 2166.68  5347.8 2168.91  5572.5 2173.19  5604.0 2175.20  5677.3 2178.17
  5683.1 2179.69  5688.3 2179.03  5735.2 2183.16  5775.0 2186.67  5834.5 2192.02
#Mann=5,-1,0
  4549.1    0.07       0  5047.7    0.05       0  5052.9    0.07       0
  5735.2     0.1       0  5775.0    0.07       0
Bank Sta=5047.7,5052.9
Exp/Cntr=0.3,0.1

Type RM Length L Ch R = 1,10903,468,468,468
BEGIN DESCRIPTION:
Stream0128 24.0
END DESCRIPTION:
XS GIS Cut Line= 3
      1795875.00     13950625.00      1795525.00     13950325.00
      1795124.98     13950325.00
#Sta/Elev= 30
  4543.5 2168.11  4564.9 2167.42  4571.5 2168.24  4579.2 2168.02  4585.8 2166.57
  4593.4 2166.97  4607.7 2165.83  4614.3 2166.19  4635.7 2164.70  4720.8 2162.36
  4735.0 2163.01  4827.2 2158.49  4848.1 2158.64  4870.0 2157.57  4922.1 2156.57
  4954.5 2154.32  4962.2 2152.61  4976.5 2151.58  4994.6 2151.46  4995.0 2150.96
  5000.1 2151.46  5001.2 2152.50  5024.5 2152.36  5034.5 2153.65  5051.9 2153.82
  5164.5 2158.64  5204.5 2161.79  5314.5 2164.68  5384.5 2169.30  5404.5 2169.27
#Mann=5,-1,0
  4543.5    0.07       0  4922.1     0.1       0  4994.6    0.05       0
  5000.1     0.1       0  5051.9    0.07       0
Bank Sta=4994.6,5000.1
Exp/Cntr=0.3,0.1

Type RM Length L Ch R = 1,10435,445,445,445
BEGIN DESCRIPTION:
Stream0128 23.0
END DESCRIPTION:
XS GIS Cut Line= 3
      1796224.99     13950724.98      1795725.00     13949925.00
      1795374.99     13949674.99
#Sta/Elev= 30
  4051.9 2185.98  4074.9 2185.10  4096.1 2182.73  4138.5 2181.66  4181.6 2176.83
  4211.7 2174.51  4379.1 2167.36  4436.9 2165.39  4442.8 2165.94  4473.5 2163.45
  4552.5 2161.50  4653.3 2161.14  4719.9 2159.85  4849.0 2154.50  4877.9 2153.54
  4900.9 2151.06  4945.2 2150.48  4951.0 2151.17  4978.9 2149.43  4979.4 2148.93
  4984.5 2149.43  5044.4 2151.35  5076.5 2151.11  5139.1 2155.87  5174.7 2157.44
  5189.4 2159.35  5239.8 2162.94  5330.6 2167.51  5346.5 2168.25  5425.4 2172.71
#Mann=7,-1,0
  4051.9    0.07       0  4849.0     0.1       0  4978.9    0.05       0
  4984.5     0.1       0  5076.5    0.07       0  5330.6     0.1       0
  5346.5    0.07       0
Bank Sta=4978.9,4984.5
Exp/Cntr=0.3,0.1

Type RM Length L Ch R = 1,9990,454,454,454
BEGIN DESCRIPTION:
Stream0128 22.0
END DESCRIPTION:
XS GIS Cut Line= 3
      1796125.01     13950025.02      1795975.00     13949625.00
      1795724.97     13949474.98
#Sta/Elev= 30
  4572.8 2159.74  4582.6 2160.16  4594.2 2159.27  4758.8 2154.78  4783.7 2153.46
  4797.1 2153.47  4819.3 2152.21  4829.1 2150.63  4861.2 2149.31  4883.4 2150.27
  4893.2 2150.14  4899.4 2149.38  4954.6 2145.99  4990.0 2145.16  5002.9 2145.36
  5004.9 2144.58  5005.4 2144.08  5010.1 2144.08  5010.6 2144.58  5023.3 2144.76
  5035.0 2147.94  5058.3 2148.38  5093.3 2152.14  5103.0 2152.24  5108.9 2152.93
  5188.6 2157.18  5233.3 2158.23  5268.2 2161.15  5278.0 2160.98  5291.6 2161.70
#Mann=5,-1,0
  4572.8    0.07       0  4883.4     0.1       0  4990.0    0.07       0
  5004.9    0.05       0  5010.6    0.07       0
Bank Sta=5004.9,5010.6
Exp/Cntr=0.3,0.1

Type RM Length L Ch R = 1,9536,452,452,452
BEGIN DESCRIPTION:
Stream0128 21.0
END DESCRIPTION:
XS GIS Cut Line= 3
      1796624.99     13949674.99      1796375.00     13949475.00
      1796175.03     13949325.02
#Sta/Elev= 30
  4684.7 2157.58  4720.7 2157.06  4727.1 2155.03  4784.7 2150.77  4812.7 2146.61
  4819.9 2146.67  4840.8 2144.19  4846.7 2144.24  4863.2 2143.07  4869.6 2141.54
  4898.4 2141.19  4919.2 2139.24  4927.2 2139.57  4933.6 2138.54  4962.4 2137.38
  4976.8 2138.04  4988.4 2137.04  4988.8 2136.54  4994.1 2137.04  5012.1 2138.18
  5018.4 2140.37  5041.3 2142.47  5047.5 2144.07  5068.4 2146.27  5112.1 2147.35
  5118.4 2148.23  5154.8 2149.29  5162.1 2150.36  5193.5 2151.12  5254.8 2152.05
#Mann=5,-1,0
  4684.7    0.07       0  4846.7     0.1       0  4988.4    0.05       0
  4994.1     0.1       0  5193.5    0.07       0
Bank Sta=4988.4,4994.1
Exp/Cntr=0.3,0.1

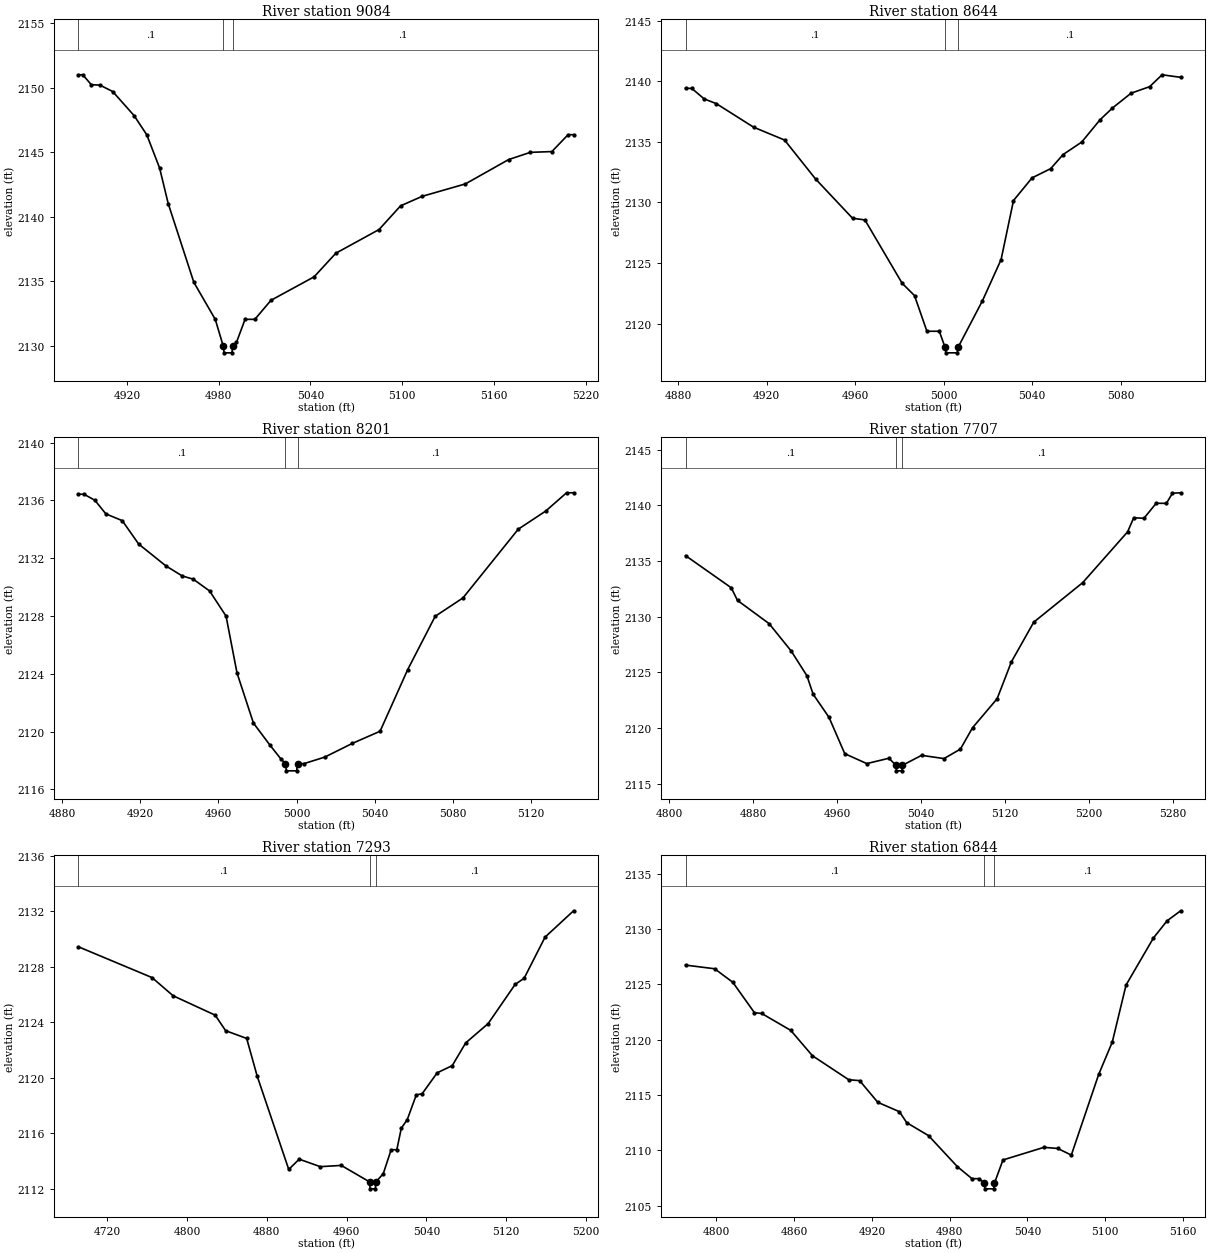
Type RM Length L Ch R = 1,9084,440,440,440
BEGIN DESCRIPTION:
Stream0128 20.0
END DESCRIPTION:
XS GIS Cut Line= 3
      1796825.01     13949425.01      1796775.00     13949325.00
      1796624.97     13949174.97
#Sta/Elev= 30
  4888.2 2151.02  4891.0 2151.02  4896.6 2150.25  4902.2 2150.22  4910.6 2149.72
  4924.6 2147.85  4932.9 2146.36  4941.3 2143.78  4946.9 2141.03  4963.7 2134.91
  4977.7 2132.04  4983.0 2129.94  4983.5 2129.44  4988.6 2129.44  4989.1 2129.94
  4991.6 2130.25  4997.2 2132.04  5003.6 2132.04  5014.2 2133.52  5042.4 2135.34
  5056.6 2137.17  5084.9 2139.01  5099.0 2140.85  5113.2 2141.59  5141.4 2142.55
  5169.7 2144.44  5183.9 2145.00  5198.0 2145.06  5208.6 2146.37  5212.2 2146.37
#Mann=3,-1,0
  4888.2     0.1       0  4983.0    0.05       0  4989.1     0.1       0
Bank Sta=4983,4989.1
Exp/Cntr=0.3,0.1

Type RM Length L Ch R = 1,8644,443,443,443
BEGIN DESCRIPTION:
Stream0128 19.0
END DESCRIPTION:
XS GIS Cut Line= 3
      1797124.99     13949124.97      1797075.00     13949025.00
      1797024.99     13948924.98
#Sta/Elev= 30
  4883.4 2139.41  4886.2 2139.41  4891.8 2138.54  4897.3 2138.15  4914.1 2136.21
  4928.1 2135.15  4942.1 2131.94  4958.8 2128.70  4964.4 2128.56  4981.2 2123.34
  4986.8 2122.32  4992.4 2119.38  4998.0 2119.38  5000.5 2118.10  5001.0 2117.60
  5006.1 2117.60  5006.6 2118.10  5017.5 2121.90  5025.9 2125.29  5031.5 2130.16
  5039.9 2132.03  5048.3 2132.79  5053.9 2133.95  5062.3 2134.98  5070.6 2136.82
  5076.2 2137.79  5084.6 2139.01  5093.0 2139.55  5098.6 2140.53  5107.0 2140.32
#Mann=3,-1,0
  4883.4     0.1       0  5000.5    0.05       0  5006.6     0.1       0
Bank Sta=5000.5,5006.6
Exp/Cntr=0.3,0.1

Type RM Length L Ch R = 1,8201,494,494,494
BEGIN DESCRIPTION:
Stream0128 18.0
END DESCRIPTION:
XS GIS Cut Line= 3
      1797475.01     13948875.02      1797425.00     13948775.00
      1797324.97     13948674.97
#Sta/Elev= 30
  4888.4 2136.43  4891.2 2136.43  4896.8 2136.01  4902.4 2135.07  4910.8 2134.60
  4919.2 2132.98  4933.1 2131.47  4941.5 2130.77  4947.1 2130.55  4955.5 2129.73
  4963.9 2127.99  4969.5 2124.06  4977.9 2120.59  4986.3 2119.07  4991.8 2118.13
  4994.3 2117.78  4994.8 2117.28  5000.0 2117.28  5000.5 2117.78  5003.8 2117.78
  5014.4 2118.23  5028.5 2119.18  5042.7 2120.02  5056.8 2124.28  5070.9 2127.98
  5085.1 2129.25  5113.4 2134.01  5127.5 2135.27  5138.1 2136.53  5141.7 2136.53
#Mann=3,-1,0
  4888.4     0.1       0  4994.3    0.05       0  5000.5     0.1       0
Bank Sta=4994.3,5000.5
Exp/Cntr=0.3,0.1

Type RM Length L Ch R = 1,7707,414,414,414
BEGIN DESCRIPTION:
Stream0128 17.0
END DESCRIPTION:
XS GIS Cut Line= 3
      1797874.97     13948574.96      1797775.00     13948425.00
      1797524.98     13948274.99
#Sta/Elev= 30
  4815.4 2135.48  4858.9 2132.60  4864.9 2131.46  4895.0 2129.38  4916.0 2126.93
  4931.0 2124.71  4937.0 2123.04  4952.1 2120.97  4967.1 2117.71  4988.1 2116.82
  5009.2 2117.30  5015.9 2116.67  5016.4 2116.17  5021.6 2116.17  5022.1 2116.67
  5040.3 2117.56  5061.7 2117.27  5077.3 2118.12  5088.9 2120.04  5112.3 2122.64
  5125.9 2125.95  5147.2 2129.51  5193.9 2133.06  5236.6 2137.61  5242.5 2138.88
  5252.2 2138.83  5263.9 2140.18  5273.6 2140.17  5279.4 2141.08  5287.2 2141.12
#Mann=3,-1,0
  4815.4     0.1       0  5015.9    0.05       0  5022.1     0.1       0
Bank Sta=5015.9,5022.1
Exp/Cntr=0.3,0.1

Type RM Length L Ch R = 1,7293,449,449,449
BEGIN DESCRIPTION:
Stream0128 16.0
END DESCRIPTION:
XS GIS Cut Line= 3
      1798075.01     13948375.04      1797975.00     13948075.00
      1797824.96     13947974.97
#Sta/Elev= 30
  4691.1 2129.44  4764.9 2127.22  4786.0 2125.91  4828.2 2124.51  4838.7 2123.39
  4859.8 2122.83  4870.3 2120.12  4902.0 2113.38  4912.5 2114.12  4933.6 2113.58
  4954.7 2113.67  4983.1 2112.48  4983.6 2111.98  4988.9 2111.98  4989.4 2112.48
  4996.8 2113.07  5004.7 2114.80  5010.4 2114.80  5014.9 2116.35  5020.9 2116.98
  5029.9 2118.75  5035.9 2118.85  5050.9 2120.35  5066.0 2120.87  5079.5 2122.51
  5102.0 2123.90  5129.1 2126.73  5138.1 2127.17  5159.1 2130.14  5187.7 2132.04
#Mann=3,-1,0
  4691.1     0.1       0  4983.1    0.05       0  4989.4     0.1       0
Bank Sta=4983.1,4989.4
Exp/Cntr=0.3,0.1

Type RM Length L Ch R = 1,6844,468,468,468
BEGIN DESCRIPTION:
Stream0128 15.0
END DESCRIPTION:
XS GIS Cut Line= 3
      1798325.01     13947925.02      1798225.00     13947725.00
      1798075.04     13947675.01
#Sta/Elev= 30
  4776.4 2126.73  4798.8 2126.40  4812.8 2125.18  4829.5 2122.43  4835.1 2122.36
  4857.5 2120.83  4874.2 2118.54  4902.2 2116.37  4910.6 2116.29  4924.6 2114.33
  4941.3 2113.48  4946.9 2112.49  4963.7 2111.32  4986.0 2108.51  4997.2 2107.43
  5002.7 2107.43  5006.7 2107.01  5007.2 2106.51  5014.0 2106.51  5014.5 2107.01
  5021.1 2109.12  5052.7 2110.26  5063.3 2110.16  5073.8 2109.56  5094.9 2116.85
  5105.4 2119.78  5116.0 2124.93  5137.1 2129.18  5147.6 2130.73  5158.1 2131.64
#Mann=3,-1,0
  4776.4     0.1       0  5006.7    0.05       0  5014.5     0.1       0
Bank Sta=5006.7,5014.5
Exp/Cntr=0.3,0.1

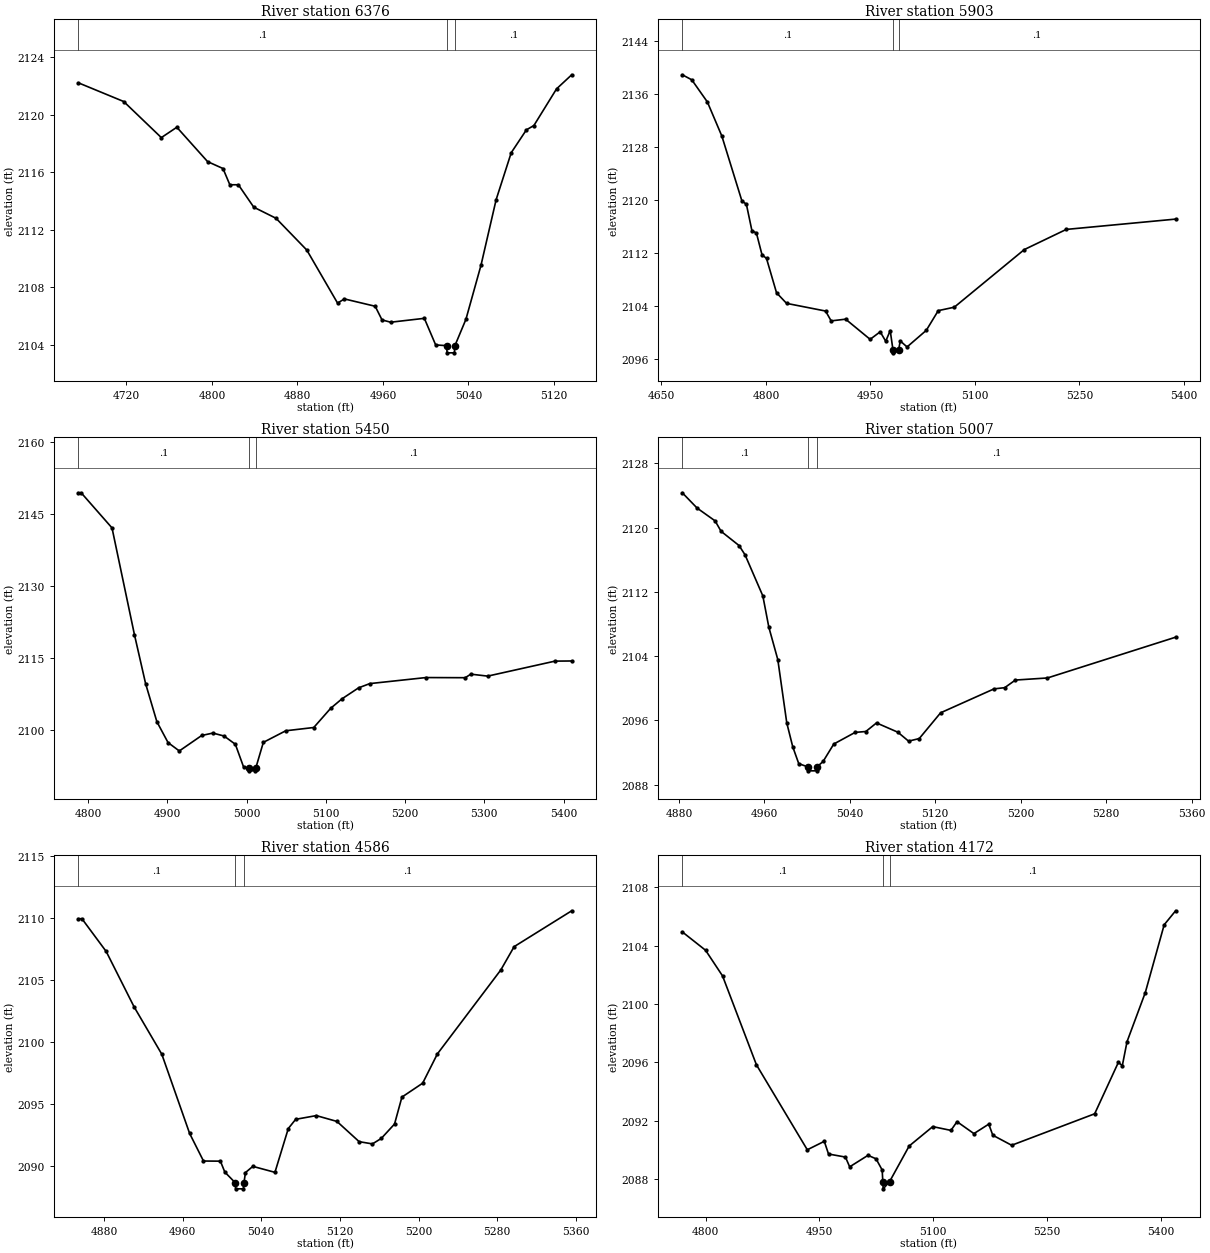
Type RM Length L Ch R = 1,6376,473,473,473
BEGIN DESCRIPTION:
Stream0128 14.0
END DESCRIPTION:
XS GIS Cut Line= 3
      1798675.01     13947625.01      1798475.00     13947375.00
      1798374.99     13947274.99
#Sta/Elev= 30
  4675.0 2122.21  4717.4 2120.91  4752.6 2118.40  4767.1 2119.12  4795.9 2116.73
  4810.3 2116.25  4816.7 2115.12  4824.7 2115.12  4839.1 2113.56  4859.9 2112.79
  4888.7 2110.58  4917.5 2106.89  4923.9 2107.18  4952.7 2106.67  4959.1 2105.72
  4967.2 2105.56  4998.7 2105.83  5009.3 2103.98  5019.5 2103.93  5020.0 2103.43
  5026.8 2103.43  5027.3 2103.93  5037.6 2105.76  5051.7 2109.52  5065.9 2114.09
  5080.0 2117.35  5094.2 2118.94  5101.2 2119.24  5122.4 2121.79  5136.6 2122.77
#Mann=3,-1,0
  4675.0     0.1       0  5019.5    0.05       0  5027.3     0.1       0
Bank Sta=5019.5,5027.3
Exp/Cntr=0.3,0.1

Type RM Length L Ch R = 1,5903,453,453,453
BEGIN DESCRIPTION:
Stream0128 13.0
END DESCRIPTION:
XS GIS Cut Line= 3
      1799024.99     13946825.00      1798775.00     13947025.00
      1798388.84     13946985.74
#Sta/Elev= 30
  4679.9 2138.93  4693.5 2138.17  4715.9 2134.82  4736.7 2129.66  4765.5 2119.85
  4771.9 2119.36  4779.9 2115.34  4786.3 2115.01  4794.3 2111.73  4800.8 2111.16
  4815.2 2105.97  4829.6 2104.37  4885.6 2103.21  4893.6 2101.72  4914.4 2101.98
  4949.6 2098.93  4964.0 2100.07  4972.0 2098.64  4978.4 2100.26  4982.3 2097.39
  4982.8 2096.89  4990.6 2097.39  4992.8 2098.69  5002.6 2097.78  5030.2 2100.29
  5047.4 2103.27  5070.4 2103.79  5170.9 2112.50  5231.2 2115.55  5388.2 2117.11
#Mann=3,-1,0
  4679.9     0.1       0  4982.3    0.05       0  4990.6     0.1       0
Bank Sta=4982.3,4990.6
Exp/Cntr=0.3,0.1

Type RM Length L Ch R = 1,5450,443,443,443
BEGIN DESCRIPTION:
Stream0128 12.0
END DESCRIPTION:
XS GIS Cut Line= 3
      1798874.99     13946475.01      1798725.00     13946625.00
      1798430.02     13946910.01
#Sta/Elev= 30
  4787.9 2149.44  4791.4 2149.44  4830.3 2142.11  4858.6 2119.84  4872.7 2109.61
  4886.9 2101.68  4901.0 2097.32  4915.2 2095.58  4943.5 2098.81  4957.6 2099.31
  4971.7 2098.69  4985.9 2096.97  4996.5 2092.13  5002.6 2091.93  5003.1 2091.43
  5011.0 2091.43  5011.5 2091.93  5021.2 2097.37  5049.5 2099.79  5084.8 2100.47
  5106.1 2104.47  5120.3 2106.44  5141.4 2108.75  5155.5 2109.63  5226.3 2110.89
  5275.9 2110.86  5282.9 2111.60  5304.2 2111.19  5389.1 2114.32  5410.2 2114.35
#Mann=3,-1,0
  4787.9     0.1       0  5002.6    0.05       0  5011.5     0.1       0
Bank Sta=5002.6,5011.5
Exp/Cntr=0.3,0.1

Type RM Length L Ch R = 1,5007,421,421,421
BEGIN DESCRIPTION:
Stream0128 11.0
END DESCRIPTION:
XS GIS Cut Line= 3
      1798474.98     13946225.03      1798425.00     13946325.00
      1798425.00     13946675.04
#Sta/Elev= 30
  4883.2 2124.35  4897.1 2122.44  4913.9 2120.85  4919.5 2119.55  4936.3 2117.78
  4941.9 2116.63  4958.6 2111.50  4964.2 2107.61  4972.6 2103.57  4981.0 2095.68
  4986.6 2092.70  4992.2 2090.61  5000.5 2090.21  5001.0 2089.71  5008.9 2089.71
  5009.4 2090.21  5015.0 2090.88  5025.0 2093.05  5045.0 2094.50  5055.0 2094.61
  5065.0 2095.68  5085.0 2094.52  5095.0 2093.41  5105.0 2093.73  5125.0 2096.94
  5175.0 2099.92  5185.0 2100.07  5195.0 2101.02  5225.0 2101.28  5345.0 2106.36
#Mann=3,-1,0
  4883.2     0.1       0  5000.5    0.05       0  5009.4     0.1       0
Bank Sta=5000.5,5009.4
Exp/Cntr=0.3,0.1

Type RM Length L Ch R = 1,4586,414,414,414
BEGIN DESCRIPTION:
Stream0128 10.0
END DESCRIPTION:
XS GIS Cut Line= 3
      1798175.02     13946024.98      1798075.00     13946125.00
      1797875.00     13946425.00
#Sta/Elev= 30
  4853.9 2109.92  4857.5 2109.92  4882.2 2107.28  4910.5 2102.83  4938.8 2099.00
  4967.1 2092.62  4981.2 2090.40  4998.4 2090.39  5002.9 2089.51  5013.4 2088.66
  5013.9 2088.16  5021.9 2088.16  5022.4 2088.66  5023.9 2089.47  5031.4 2089.97
  5053.9 2089.49  5067.5 2093.02  5075.0 2093.76  5096.0 2094.06  5117.0 2093.59
  5139.6 2091.96  5153.1 2091.78  5162.1 2092.22  5175.6 2093.38  5183.1 2095.55
  5204.2 2096.67  5219.2 2099.03  5283.8 2105.80  5297.3 2107.67  5355.9 2110.56
#Mann=3,-1,0
  4853.9     0.1       0  5013.4    0.05       0  5022.4     0.1       0
Bank Sta=5013.4,5022.4
Exp/Cntr=0.3,0.1

Type RM Length L Ch R = 1,4172,479,479,479
BEGIN DESCRIPTION:
Stream0128 9.0
END DESCRIPTION:
XS GIS Cut Line= 3
      1797975.00     13945775.00      1797775.00     13945875.00
      1797625.00     13946274.99
#Sta/Elev= 30
  4769.1 2104.95  4799.8 2103.69  4822.2 2101.93  4866.9 2095.83  4934.0 2090.00
  4956.4 2090.58  4962.0 2089.71  4984.3 2089.50  4989.9 2088.83  5014.1 2089.62
  5024.7 2089.38  5032.8 2088.61  5033.6 2087.82  5034.1 2087.32  5042.6 2087.82
  5068.4 2090.26  5099.5 2091.59  5123.5 2091.33  5131.5 2091.93  5153.8 2091.11
  5173.4 2091.76  5178.7 2091.00  5203.6 2090.31  5313.1 2092.47  5344.3 2095.99
  5349.6 2095.78  5355.8 2097.42  5379.9 2100.79  5404.8 2105.44  5419.9 2106.40
#Mann=3,-1,0
  4769.1     0.1       0  5033.6    0.05       0  5042.6     0.1       0
Bank Sta=5033.6,5042.6
Exp/Cntr=0.3,0.1

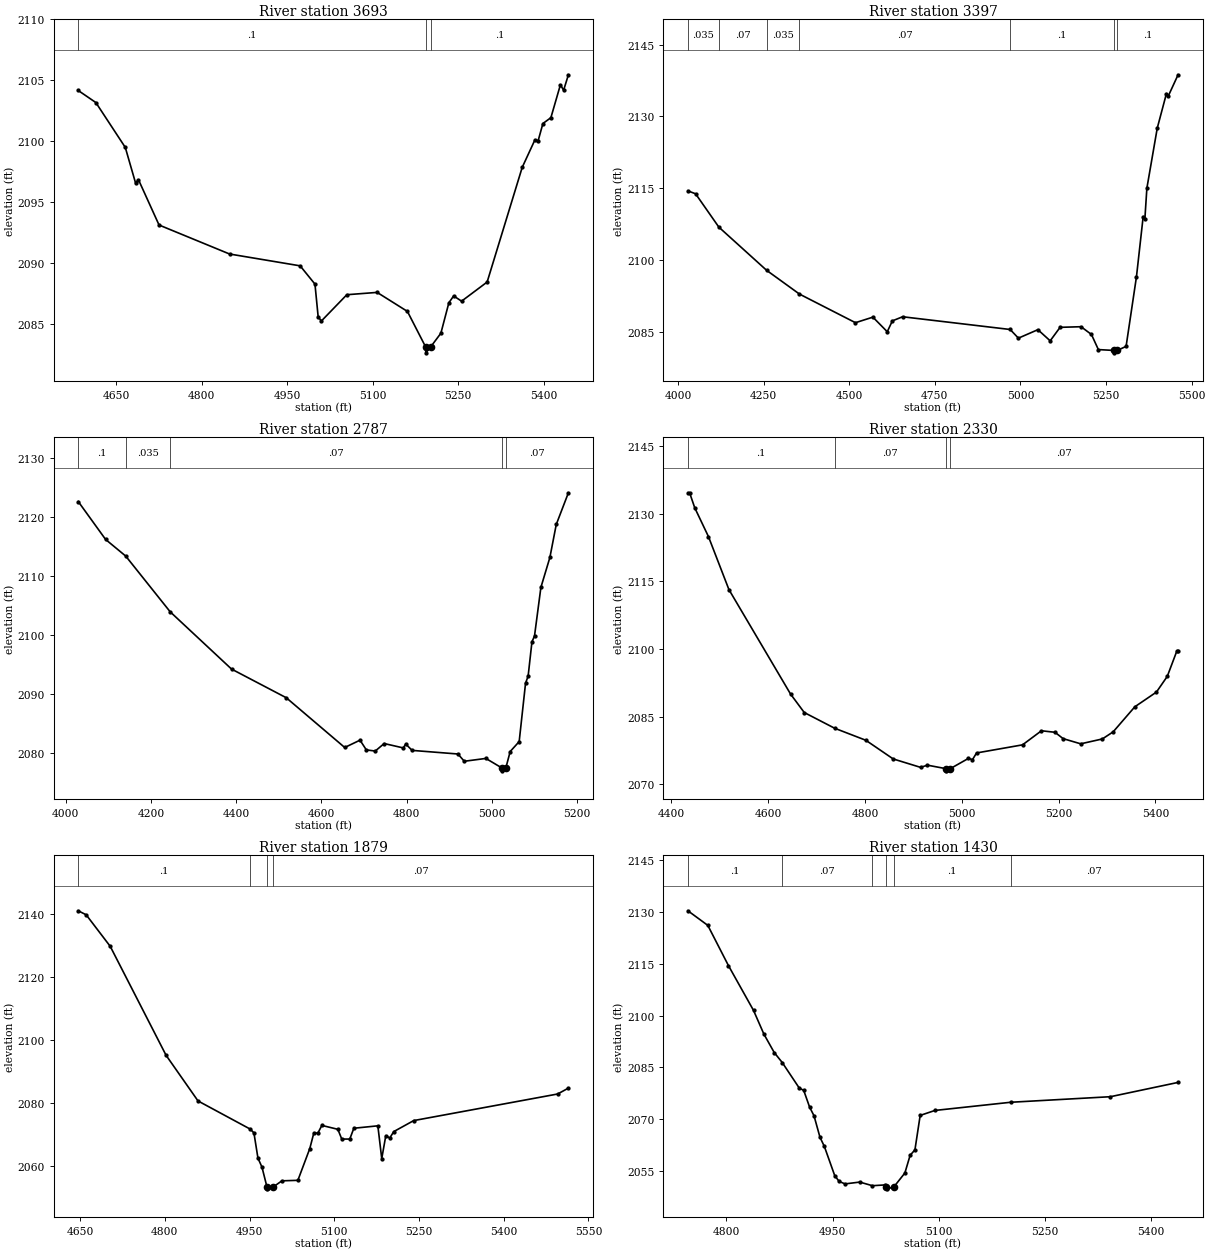
Type RM Length L Ch R = 1,3693,296,296,296
BEGIN DESCRIPTION:
Stream0128 8.0
END DESCRIPTION:
XS GIS Cut Line= 3
      1797974.99     13945375.00      1797575.00     13945475.00
      1797175.02     13945674.99
#Sta/Elev= 30
  4583.6 2104.16  4614.5 2103.17  4666.1 2099.49  4684.1 2096.57  4689.2 2096.84
  4725.3 2093.12  4849.0 2090.74  4972.7 2089.77  4998.7 2088.27  5004.3 2085.59
  5009.9 2085.24  5054.6 2087.40  5107.7 2087.59  5160.8 2086.03  5192.6 2083.13
  5193.1 2082.63  5201.8 2083.13  5219.5 2084.24  5233.5 2086.74  5241.9 2087.30
  5255.8 2086.87  5300.6 2088.44  5362.1 2097.85  5384.4 2100.11  5390.0 2100.03
  5398.4 2101.45  5412.4 2101.93  5429.1 2104.63  5434.7 2104.18  5443.1 2105.45
#Mann=3,-1,0
  4583.6     0.1       0  5192.6    0.05       0  5201.8     0.1       0
Bank Sta=5192.6,5201.8
Exp/Cntr=0.3,0.1

Type RM Length L Ch R = 1,3397,610,610,610
BEGIN DESCRIPTION:
Stream0128 7.0
END DESCRIPTION:
XS GIS Cut Line= 3
      1797974.98     13944425.03      1797361.15     13945327.30
      1797024.97     13945275.00
#Sta/Elev= 30
  4028.9 2114.43  4051.3 2113.82  4119.3 2106.85  4259.0 2097.81  4354.7 2092.86
  4518.2 2086.88  4569.1 2088.04  4611.1 2084.99  4626.0 2087.26  4655.9 2088.12
  4970.0 2085.46  4994.1 2083.65  5051.0 2085.42  5086.9 2083.09  5115.8 2085.91
  5177.0 2086.04  5207.4 2084.42  5227.6 2081.26  5273.6 2081.08  5274.1 2080.58
  5282.8 2081.08  5308.6 2081.93  5338.9 2096.49  5358.5 2109.06  5363.5 2108.63
  5369.3 2114.99  5399.6 2127.54  5426.4 2134.76  5431.5 2134.20  5460.4 2138.69
#Mann=7,-1,0
  4028.9   0.035       0  4119.3    0.07       0  4259.0   0.035       0
  4354.7    0.07       0  4970.0     0.1       0  5273.6    0.05       0
  5282.8     0.1       0
Bank Sta=5273.6,5282.8
Exp/Cntr=0.3,0.1

Type RM Length L Ch R = 1,2787,457,457,457
BEGIN DESCRIPTION:
Stream0128 6.0
END DESCRIPTION:
XS GIS Cut Line= 3
      1797975.03     13944274.98      1797175.00     13944825.00
      1797025.03     13944924.98
#Sta/Elev= 30
  4029.1 2122.59  4093.4 2116.17  4140.6 2113.36  4245.0 2103.93  4389.1 2094.24
  4517.6 2089.39  4654.9 2080.97  4690.8 2082.21  4705.7 2080.56  4726.6 2080.37
  4747.6 2081.64  4792.3 2080.90  4798.3 2081.55  4813.2 2080.48  4920.8 2079.87
  4935.7 2078.64  4986.4 2079.12  5023.7 2077.52  5024.2 2077.02  5033.3 2077.52
  5043.5 2080.29  5064.6 2081.97  5079.6 2091.87  5085.6 2093.03  5094.6 2098.85
  5100.6 2099.84  5115.6 2108.06  5136.7 2113.12  5151.7 2118.71  5180.2 2124.07
#Mann=5,-1,0
  4029.1     0.1       0  4140.6   0.035       0  4245.0    0.07       0
  5023.7    0.05       0  5033.3    0.07       0
Bank Sta=5023.7,5033.3
Exp/Cntr=0.3,0.1

Type RM Length L Ch R = 1,2330,451,451,451
BEGIN DESCRIPTION:
Stream0128 5.0
END DESCRIPTION:
XS GIS Cut Line= 3
      1797724.97     13944025.03      1797325.00     13944425.00
      1796925.04     13944624.98
#Sta/Elev= 30
  4434.0 2134.69  4437.5 2134.69  4448.1 2131.36  4476.4 2124.97  4518.8 2113.18
  4646.1 2089.99  4674.4 2085.89  4737.2 2082.40  4801.6 2079.73  4858.2 2075.58
  4914.8 2073.71  4928.9 2074.20  4966.3 2073.44  4966.8 2072.94  4976.4 2073.44
  5013.6 2075.70  5022.0 2075.42  5030.4 2076.91  5125.4 2078.71  5164.5 2081.84
  5192.5 2081.50  5209.3 2080.09  5245.6 2078.94  5290.3 2080.02  5312.7 2081.60
  5357.4 2087.16  5402.1 2090.43  5424.5 2093.92  5444.1 2099.50  5446.8 2099.50
#Mann=4,-1,0
  4434.0     0.1       0  4737.2    0.07       0  4966.3    0.05       0
  4976.4    0.07       0
Bank Sta=4966.3,4976.4
Exp/Cntr=0.3,0.1

Type RM Length L Ch R = 1,1879,449,449,449
BEGIN DESCRIPTION:
Stream0128 4.0
END DESCRIPTION:
XS GIS Cut Line= 3
      1797525.00     13943775.00      1797275.00     13944025.00
      1796919.81     13944397.02
#Sta/Elev= 30
  4646.7 2140.99  4660.8 2139.71  4703.3 2129.72  4802.3 2095.13  4858.8 2080.67
  4951.2 2071.74  4957.8 2070.53  4964.9 2062.53  4972.0 2059.69  4981.0 2053.29
  4981.5 2052.79  4991.2 2053.29  5007.3 2055.33  5035.6 2055.49  5056.7 2065.57
  5063.9 2070.54  5070.9 2070.44  5078.1 2072.91  5106.4 2071.67  5113.3 2068.58
  5127.5 2068.58  5134.7 2072.01  5177.2 2072.78  5184.1 2062.37  5191.3 2069.67
  5198.2 2068.90  5205.5 2070.96  5240.7 2074.44  5495.5 2082.87  5514.6 2084.74
#Mann=4,-1,0
  4646.7     0.1       0  4951.2    0.07       0  4981.0    0.05       0
  4991.2    0.07       0
Bank Sta=4981,4991.2
Exp/Cntr=0.3,0.1

Type RM Length L Ch R = 1,1430,444,444,444
BEGIN DESCRIPTION:
Stream0128 3.0
END DESCRIPTION:
XS GIS Cut Line= 3
      1797225.00     13943525.00      1797025.00     13943675.00
      1796700.71     13943975.63
#Sta/Elev= 30
  4745.7 2130.35  4773.8 2126.12  4803.0 2114.44  4838.4 2101.46  4853.0 2094.61
  4867.6 2089.27  4878.9 2086.38  4903.0 2078.96  4909.2 2078.32  4917.6 2073.43
  4923.8 2070.93  4932.2 2064.72  4938.4 2062.05  4953.0 2053.62  4959.2 2051.93
  4967.6 2051.20  4988.4 2051.73  5006.2 2050.68  5023.8 2050.90  5026.0 2050.27
  5026.5 2049.77  5036.3 2050.27  5052.1 2054.36  5059.5 2059.49  5066.3 2061.07
  5073.7 2071.05  5094.6 2072.49  5201.6 2074.86  5342.4 2076.47  5437.9 2080.61
#Mann=6,-1,0
  4745.7     0.1       0  4878.9    0.07       0  5006.2     0.1       0
  5026.0    0.05       0  5036.3     0.1       0  5201.6    0.07       0
Bank Sta=5026,5036.3
Exp/Cntr=0.3,0.1