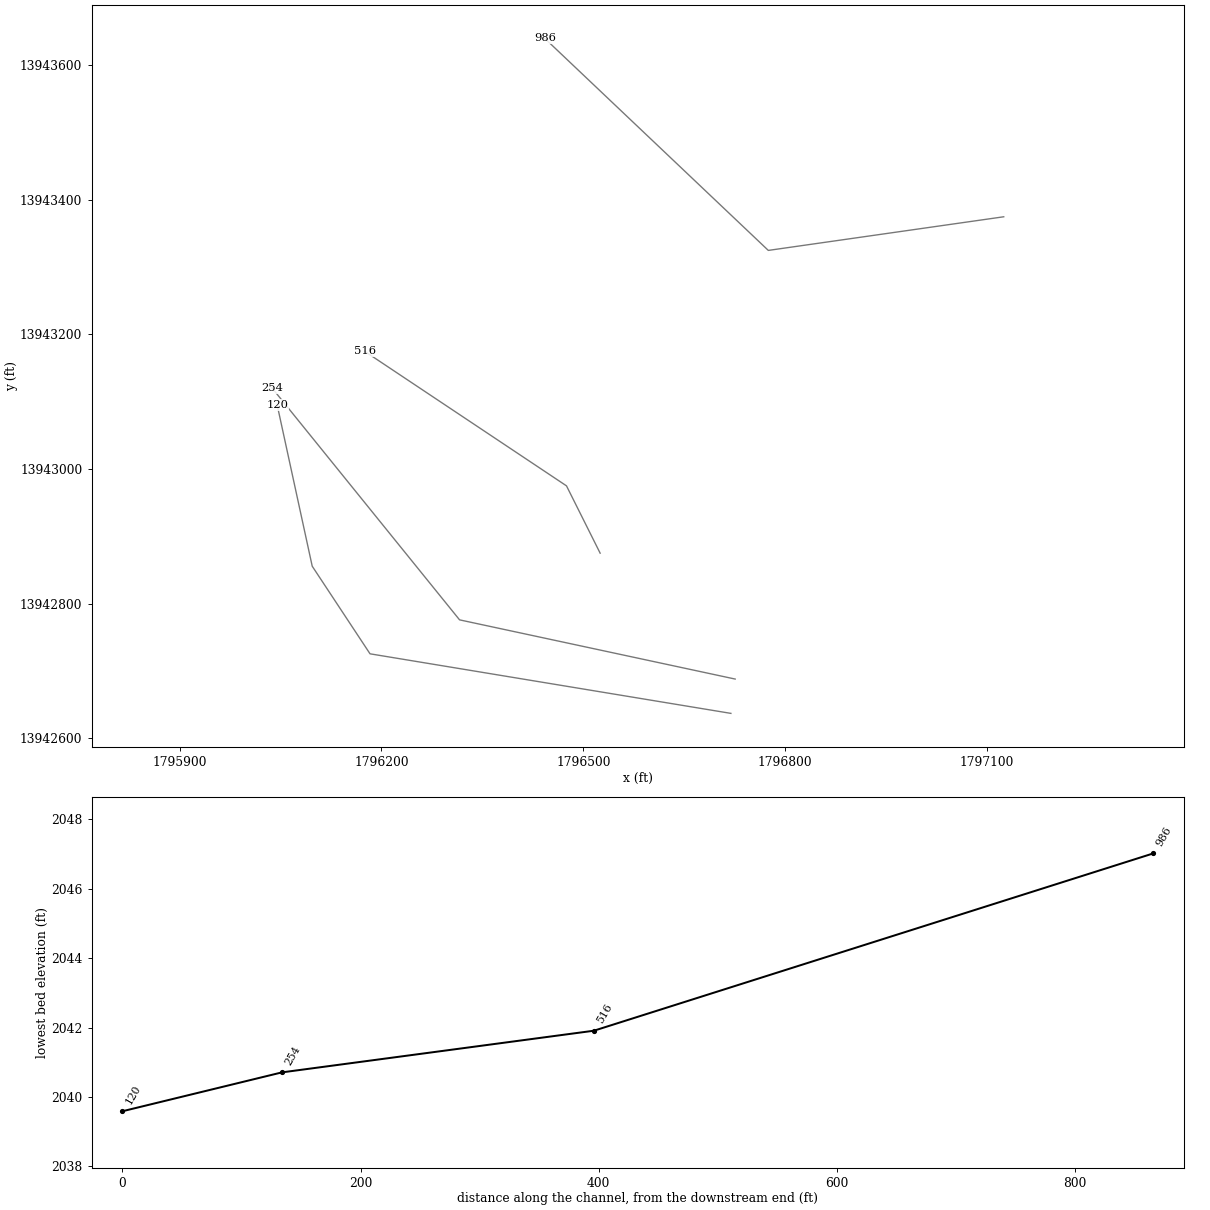
HEC-RAS study Stream0128.prj: Stream0128 Base Level Engineering

--- Stream0128.g01 (geometry) --- (continued)

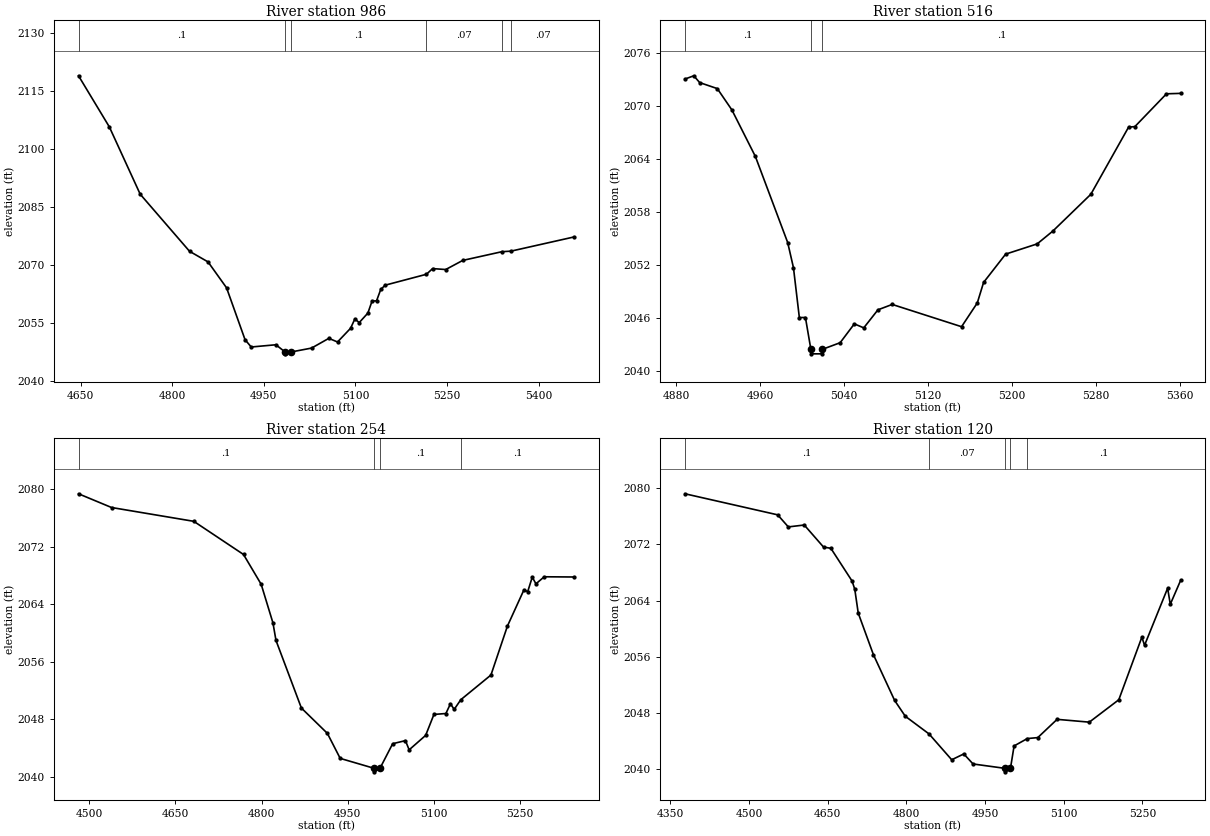
Type RM Length L Ch R = 1,986,470,470,470
BEGIN DESCRIPTION:
Stream0128 2.0
END DESCRIPTION:
XS GIS Cut Line= 3
      1797124.95     13943374.99      1796775.00     13943325.00
      1796442.62     13943640.24
#Sta/Elev= 30
  4646.5 2119.01  4697.0 2105.77  4747.5 2088.35  4828.3 2073.57  4858.6 2070.82
  4888.9 2064.12  4919.2 2050.68  4929.3 2048.79  4969.7 2049.37  4984.6 2047.52
  4985.1 2047.02  4995.2 2047.52  5028.1 2048.51  5056.4 2051.03  5070.6 2050.09
  5092.0 2053.64  5098.9 2056.02  5106.2 2055.12  5120.3 2057.57  5127.2 2060.71
  5134.5 2060.73  5141.4 2063.70  5148.7 2064.80  5216.2 2067.62  5226.3 2069.09
  5247.8 2068.85  5275.7 2071.21  5340.0 2073.47  5354.4 2073.60  5458.1 2077.29
#Mann=6,-1,0
  4646.5     0.1       0  4984.6    0.05       0  4995.2     0.1       0
  5216.2    0.07       0  5340.0     0.1       0  5354.4    0.07       0
Bank Sta=4984.6,4995.2
Exp/Cntr=0.3,0.1

Type RM Length L Ch R = 1,516,262,262,262
BEGIN DESCRIPTION:
Stream0128 1.0
END DESCRIPTION:
XS GIS Cut Line= 3
      1796525.01     13942874.98      1796475.00     13942975.00
      1796174.99     13943175.01
#Sta/Elev= 30
  4888.4 2073.00  4896.8 2073.37  4902.4 2072.60  4919.2 2071.92  4933.1 2069.51
  4955.5 2064.24  4986.3 2054.50  4991.8 2051.65  4997.4 2046.02  5003.2 2046.02
  5008.4 2042.41  5008.9 2041.91  5018.6 2041.91  5019.1 2042.41  5036.3 2043.17
  5049.8 2045.30  5058.8 2044.85  5072.3 2046.89  5085.9 2047.50  5152.0 2044.98
  5167.0 2047.67  5173.0 2049.99  5194.0 2053.19  5224.1 2054.35  5239.1 2055.81
  5275.2 2059.96  5311.2 2067.56  5317.2 2067.62  5347.3 2071.33  5360.8 2071.38
#Mann=3,-1,0
  4888.4     0.1       0  5008.4    0.05       0  5019.1     0.1       0
Bank Sta=5008.4,5019.1
Exp/Cntr=0.3,0.1

Type RM Length L Ch R = 1,254,134,134,134
BEGIN DESCRIPTION:
Stream0128 0.0
END DESCRIPTION:
XS GIS Cut Line= 3
      1796725.74     13942687.81      1796316.05     13942775.81
      1796037.25     13943120.55
#Sta/Elev= 30
  4481.4 2079.37  4538.9 2077.46  4682.0 2075.54  4768.5 2070.93  4799.2 2066.79
  4819.7 2061.42  4825.0 2058.98  4869.2 2049.58  4914.4 2046.06  4936.7 2042.58
  4995.3 2041.21  4995.8 2040.71  5006.0 2041.21  5028.0 2044.62  5050.2 2045.05
  5056.7 2043.77  5085.4 2045.78  5099.8 2048.69  5120.6 2048.82  5128.6 2050.18
  5135.0 2049.39  5146.6 2050.74  5199.0 2054.17  5227.7 2060.98  5256.5 2066.03
  5262.9 2065.75  5270.9 2067.78  5277.3 2066.85  5291.7 2067.83  5343.8 2067.80
#Mann=4,-1,0
  4481.4     0.1       0  4995.3    0.05       0  5006.0     0.1       0
  5146.6     0.1       0
Bank Sta=4995.3,5006
Exp/Cntr=0.3,0.1

Type RM Length L Ch R = 1,120,0,0,0
BEGIN DESCRIPTION:
Stream0128 0.1
END DESCRIPTION:
XS GIS Cut Line= 4
      1796719.38     13942636.80      1796182.96     13942725.34
      1796097.02     13942855.55      1796044.94     13943095.16
#Sta/Elev= 30
  4378.1 2079.21  4554.8 2076.21  4575.1 2074.49  4605.5 2074.76  4642.2 2071.62
  4656.2 2071.44  4696.7 2066.77  4701.8 2065.60  4708.4 2062.21  4737.3 2056.29
  4777.8 2049.76  4798.1 2047.51  4843.4 2044.99  4886.6 2041.31  4909.6 2042.14
  4927.3 2040.71  4987.9 2040.09  4988.4 2039.59  4998.6 2040.09  5005.5 2043.28
  5030.7 2044.33  5050.7 2044.47  5087.5 2047.07  5148.9 2046.67  5205.1 2049.86
  5249.1 2058.78  5254.2 2057.62  5298.2 2065.75  5303.3 2063.47  5323.0 2066.87
#Mann=5,-1,0
  4378.1     0.1       0  4843.4    0.07       0  4987.9    0.05       0
  4998.6    0.07       0  5030.7     0.1       0
Bank Sta=4987.9,4998.6
Exp/Cntr=0.3,0.1

Chan Stop Cuts=-1