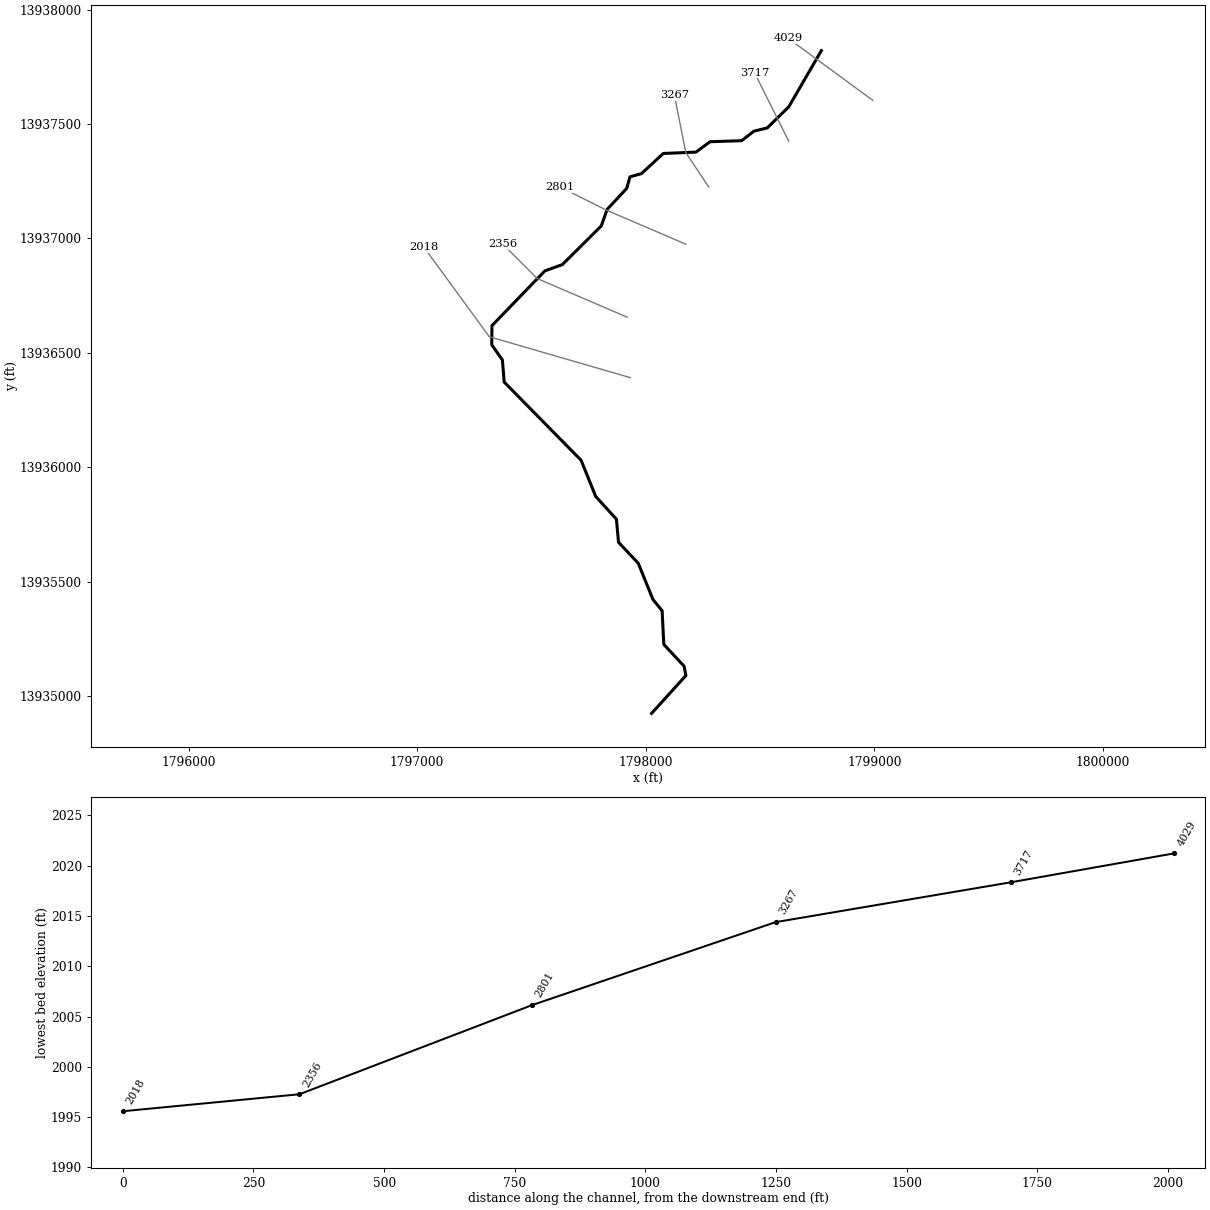
--- Stream0130.prj (project) ---

Proj Title=Stream0130 Base Level Engineering
Current Plan=p01
Default Exp/Contr=0.3,0.1
English Units
Geom File=g01
Flow File=f01
Plan File=p01
BEGIN DESCRIPTION:
Stream0130
END DESCRIPTION:

--- Stream0130.p01 (plan) ---

Plan Title=Multiple Run
Short Identifier=Multiple
Geom File=g01
Flow File=f01
Subcritical Flow
K Sum by GR= 0
Std Step Tol= 0.01
Critical Tol= 0.01
Num of Std Step Trials= 20
Max Error Tol= 0.3
Flow Tol Ratio= 0.001
Split Flow NTrial= 30
Split Flow Tol= 0.02
Split Flow Ratio= 0.02
Log Output Level= 0
Friction Slope Method= 1
Unsteady Friction Slope Method= 2
Unsteady Bridges Friction Slope Method= 1
Parabolic Critical Depth
Global Vel Dist=  1 , 1 , 1
Global Log Level= 0
CheckData=True
Encroach Param= -1, 0, 0, 0
BEGIN DESCRIPTION:
Multiple Run
END DESCRIPTION:

--- Stream0130.f01 (steady flow) ---

Flow Title=Multiple
Number of Profiles=7
Profile Names=10-year,25-year,50-year,1pct_min,100-year,1pct_plu,500-year
River Rch & RM= Stream0130,Reach-1,4029
    1215    2105    2963    2014    4019    8019    7315
River Rch & RM= Stream0130,Reach-1,3717
    1394    2428    3428    2336    4662    9301    8530
Boundary for River Rch & Prof#=Stream0130,Reach-1,1
Up Type=0
Dn Type=3
Dn Slope=0.005
Boundary for River Rch & Prof#=Stream0130,Reach-1,2
Up Type=0
Dn Type=3
Dn Slope=0.005
Boundary for River Rch & Prof#=Stream0130,Reach-1,3
Up Type=0
Dn Type=3
Dn Slope=0.005
Boundary for River Rch & Prof#=Stream0130,Reach-1,4
Up Type=0
Dn Type=3
Dn Slope=0.005
Boundary for River Rch & Prof#=Stream0130,Reach-1,5
Up Type=0
Dn Type=3
Dn Slope=0.005
Boundary for River Rch & Prof#=Stream0130,Reach-1,6
Up Type=0
Dn Type=3
Dn Slope=0.005
Boundary for River Rch & Prof#=Stream0130,Reach-1,7
Up Type=0
Dn Type=3
Dn Slope=0.005

--- Stream0130.g01 (geometry) ---

Geom Title=Existing Conditions

River Reach=Stream0130,Reach-1
Reach XY= 30
      1798767.66     13937820.67      1798625.00     13937575.00
      1798531.08     13937483.09      1798472.83     13937468.87
      1798419.07     13937427.25      1798280.94     13937422.73
      1798219.06     13937377.27      1798076.47     13937371.45
      1797980.74     13937283.30      1797930.62     13937269.38
      1797916.70     13937219.26      1797830.87     13937127.28
      1797805.21     13937054.91      1797634.68     13936885.78
      1797558.33     13936858.35      1797326.96     13936619.11
      1797326.10     13936535.55      1797372.64     13936469.02
      1797380.52     13936372.57      1797716.86     13936031.06
      1797780.85     13935872.71      1797871.37     13935773.50
      1797880.54     13935672.58      1797966.84     13935581.05
      1798031.12     13935422.82      1798071.24     13935373.44
      1798078.56     13935226.47      1798167.52     13935131.04
      1798175.11     13935090.36      1798025.00     13934925.00

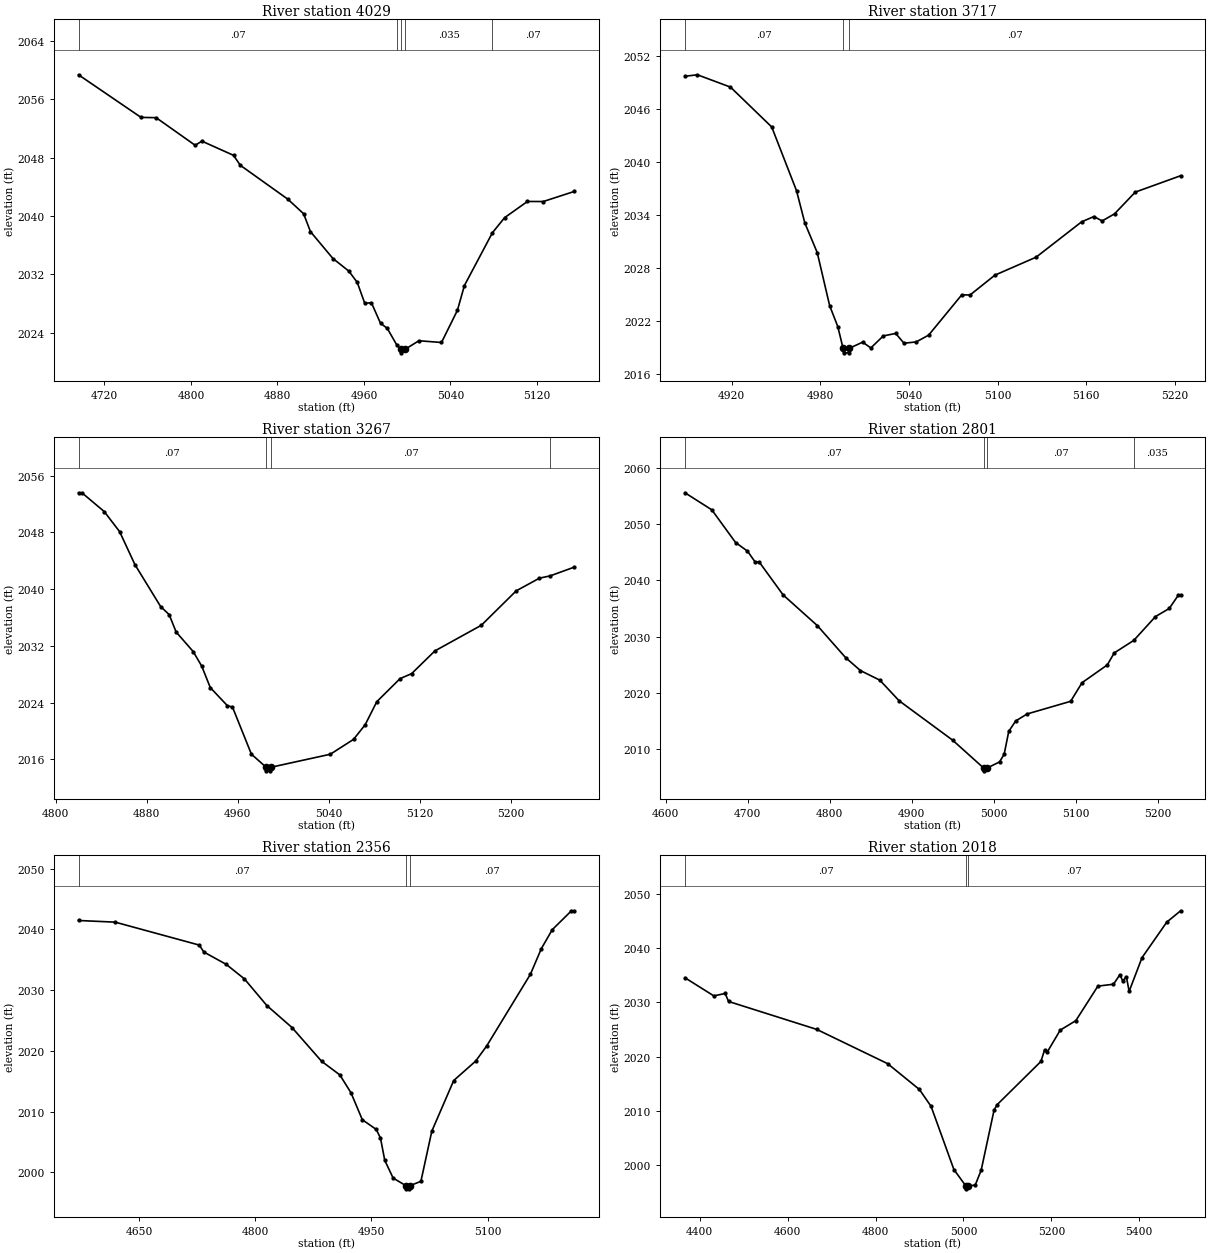
Type RM Length L Ch R = 1,4029,312,312,312
BEGIN DESCRIPTION:
Stream0130 10.0
END DESCRIPTION:
XS GIS Cut Line= 2
      1798992.95     13937603.20      1798623.13     13937874.06
#Sta/Elev= 30
  4696.0 2059.39  4753.8 2053.54  4767.8 2053.50  4803.9 2049.71  4810.1 2050.28
  4839.4 2048.33  4845.6 2046.97  4889.6 2042.31  4904.2 2040.31  4910.5 2037.86
  4931.3 2034.17  4946.0 2032.44  4953.8 2030.89  4960.7 2028.03  4966.9 2028.09
  4975.3 2025.28  4981.5 2024.59  4990.5 2022.26  4994.2 2021.72  4994.4 2021.22
  4998.2 2021.72  5010.8 2022.88  5031.7 2022.64  5046.4 2027.05  5052.9 2030.46
  5078.8 2037.71  5090.1 2039.78  5111.2 2042.00  5125.8 2041.99  5154.4 2043.37
#Mann=5,-1,0
  4696.0    0.07       0  4990.5   0.035       0  4994.2   0.035       0
  4998.2   0.035       0  5078.8    0.07       0
Bank Sta=4994.2,4998.2
Exp/Cntr=0.3,0.1

Type RM Length L Ch R = 1,3717,450,450,450
BEGIN DESCRIPTION:
Stream0130 5.0
END DESCRIPTION:
XS GIS Cut Line= 3
      1798625.01     13937424.98      1798575.00     13937525.00
      1798475.01     13937724.97
#Sta/Elev= 30
  4888.5 2049.72  4896.9 2049.89  4919.3 2048.49  4947.2 2043.97  4964.0 2036.73
  4969.6 2033.08  4978.0 2029.72  4986.4 2023.70  4991.9 2021.33  4995.5 2018.85
  4995.8 2018.35  4999.3 2018.35  4999.5 2018.85  5008.7 2019.56  5014.3 2018.91
  5022.7 2020.27  5031.1 2020.55  5036.7 2019.44  5045.0 2019.59  5053.4 2020.36
  5075.8 2024.93  5081.4 2024.91  5098.2 2027.16  5126.1 2029.20  5156.9 2033.21
  5165.2 2033.81  5170.8 2033.31  5179.2 2034.12  5193.2 2036.58  5223.9 2038.44
#Mann=3,-1,0
  4888.5    0.07       0  4995.5    0.05       0  4999.5    0.07       0
Bank Sta=4995.5,4999.5
Exp/Cntr=0.3,0.1

Type RM Length L Ch R = 1,3267,466,466,466
BEGIN DESCRIPTION:
Stream0130 4.0
END DESCRIPTION:
XS GIS Cut Line= 3
      1798275.01     13937224.98      1798175.00     13937375.00
      1798125.01     13937624.95
#Sta/Elev= 30
  4820.1 2053.60  4823.1 2053.60  4842.7 2050.95  4856.2 2048.12  4869.7 2043.45
  4892.2 2037.56  4899.7 2036.42  4905.8 2033.97  4920.8 2031.21  4928.3 2029.15
  4935.8 2026.13  4950.8 2023.58  4955.3 2023.38  4971.9 2016.74  4984.9 2014.89
  4985.1 2014.39  4988.6 2014.39  4988.9 2014.89  5041.2 2016.73  5061.6 2018.83
  5071.8 2020.89  5082.0 2024.14  5102.4 2027.39  5112.6 2028.10  5133.0 2031.30
  5173.8 2034.92  5204.4 2039.77  5224.8 2041.56  5234.2 2041.88  5255.3 2043.11
#Mann=4,-1,0
  4820.1    0.07       0  4984.9    0.05       0  4988.9    0.07       0
  5234.2   0.035       0
Bank Sta=4984.9,4988.9
Exp/Cntr=0.3,0.1

Type RM Length L Ch R = 1,2801,445,445,445
BEGIN DESCRIPTION:
Stream0130 3.0
END DESCRIPTION:
XS GIS Cut Line= 3
      1798175.03     13936974.99      1797825.00     13937125.00
      1797625.02     13937224.99
#Sta/Elev= 30
  4623.5 2055.57  4656.2 2052.54  4685.2 2046.73  4699.7 2045.20  4708.8 2043.32
  4714.2 2043.23  4743.2 2037.41  4784.9 2031.96  4819.4 2026.26  4837.5 2023.96
  4861.1 2022.26  4884.6 2018.60  4949.9 2011.59  4987.7 2006.64  4987.9 2006.14
  4992.0 2006.64  5007.1 2007.73  5012.7 2009.09  5018.3 2013.15  5026.7 2015.00
  5040.7 2016.25  5093.8 2018.50  5107.7 2021.81  5138.5 2024.97  5146.9 2027.10
  5170.8 2029.33  5197.2 2033.56  5214.0 2035.00  5225.1 2037.36  5227.9 2037.36
#Mann=4,-1,0
  4623.5    0.07       0  4987.7    0.05       0  4992.0    0.07       0
  5170.8   0.035       0
Bank Sta=4987.7,4992
Exp/Cntr=0.3,0.1

Type RM Length L Ch R = 1,2356,338,338,338
BEGIN DESCRIPTION:
Stream0130 2.0
END DESCRIPTION:
XS GIS Cut Line= 3
      1797918.43     13936656.08      1797525.00     13936825.00
      1797375.00     13936975.00
#Sta/Elev= 30
  4571.6 2041.45  4618.9 2041.18  4727.7 2037.40  4733.4 2036.27  4762.4 2034.23
  4785.9 2031.84  4814.9 2027.45  4847.4 2023.83  4885.6 2018.28  4909.2 2016.03
  4923.6 2013.09  4938.2 2008.66  4956.2 2007.06  4961.7 2005.64  4967.2 2001.98
  4978.0 1999.06  4994.8 1997.78  4995.1 1997.28  4998.9 1997.28  4999.2 1997.78
  5013.9 1998.51  5028.0 2006.77  5056.3 2015.11  5084.6 2018.30  5098.8 2020.78
  5155.3 2032.58  5169.5 2036.82  5183.6 2039.94  5208.4 2043.05  5211.9 2043.05
#Mann=3,-1,0
  4571.6    0.07       0  4994.8    0.05       0  4999.2    0.07       0
Bank Sta=4994.8,4999.2
Exp/Cntr=0.3,0.1

Type RM Length L Ch R = 1,2018,0,0,0
BEGIN DESCRIPTION:
Stream0130 1.0
END DESCRIPTION:
XS GIS Cut Line= 3
      1797932.87     13936391.71      1797315.56     13936570.55
      1797029.07     13936962.27
#Sta/Elev= 30
  4366.3 2034.53  4431.9 2031.19  4457.8 2031.63  4465.5 2030.16  4666.0 2025.01
  4827.4 2018.69  4899.7 2013.93  4926.3 2010.82  4978.3 1999.15  5005.8 1996.09
  5006.1 1995.59  5010.2 1996.09  5026.9 1996.29  5040.4 1999.04  5069.7 2010.11
  5076.5 2011.10  5176.3 2019.09  5184.8 2021.25  5191.0 2020.86  5220.3 2024.87
  5255.8 2026.62  5306.0 2032.99  5341.5 2033.34  5356.2 2035.11  5362.4 2033.96
  5370.9 2034.70  5377.1 2032.02  5406.4 2038.24  5462.8 2044.80  5494.3 2046.89
#Mann=3,-1,0
  4366.3    0.07       0  5005.8    0.05       0  5010.2    0.07       0
Bank Sta=5005.8,5010.2
Exp/Cntr=0.3,0.1

Chan Stop Cuts=-1