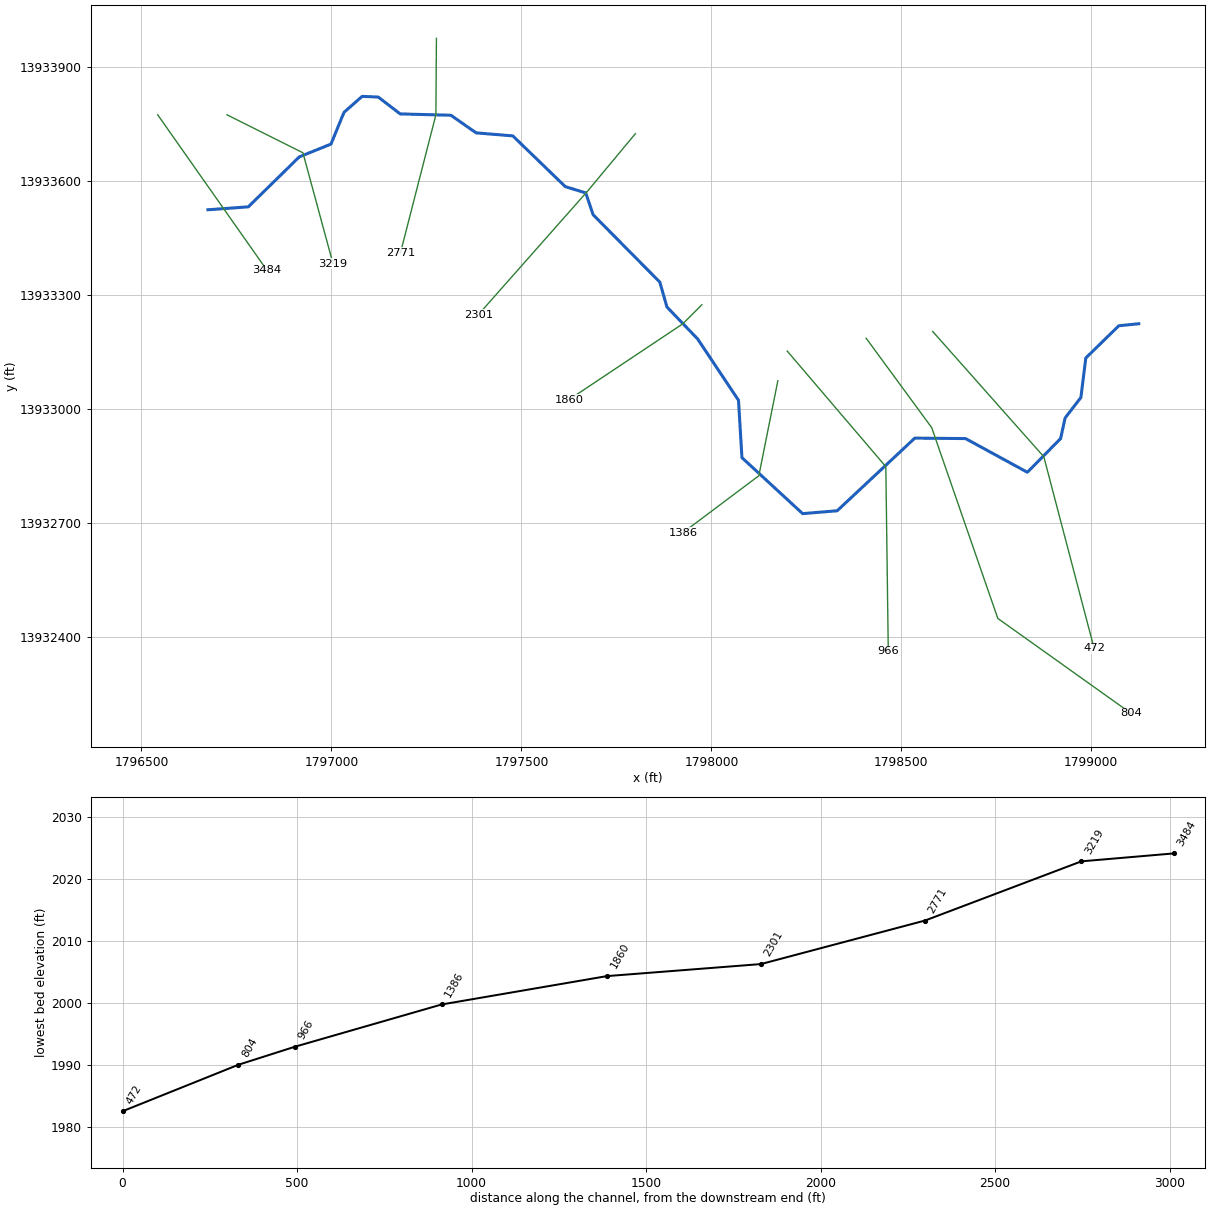
--- Stream0132.prj (project) ---

Proj Title=Stream0132 Base Level Engineering
Current Plan=p01
Default Exp/Contr=0.3,0.1
English Units
Geom File=g01
Flow File=f01
Plan File=p01
BEGIN DESCRIPTION:
Stream0132
END DESCRIPTION:

--- Stream0132.p01 (plan) ---

Plan Title=Multiple Run
Short Identifier=Multiple
Geom File=g01
Flow File=f01
Subcritical Flow
K Sum by GR= 0
Std Step Tol= 0.01
Critical Tol= 0.01
Num of Std Step Trials= 20
Max Error Tol= 0.3
Flow Tol Ratio= 0.001
Split Flow NTrial= 30
Split Flow Tol= 0.02
Split Flow Ratio= 0.02
Log Output Level= 0
Friction Slope Method= 1
Unsteady Friction Slope Method= 2
Unsteady Bridges Friction Slope Method= 1
Parabolic Critical Depth
Global Vel Dist=  1 , 1 , 1
Global Log Level= 0
CheckData=True
Encroach Param= -1, 0, 0, 0
BEGIN DESCRIPTION:
Multiple Run
END DESCRIPTION:

--- Stream0132.f01 (steady flow) ---

Flow Title=Multiple
Number of Profiles=7
Profile Names=10-year,25-year,50-year,1pct_min,100-year,1pct_plu,500-year
River Rch & RM= Stream0132,Reach-1,3484
    1143    1970    2763    1872    3735    7453    6750
Boundary for River Rch & Prof#=Stream0132,Reach-1,1
Up Type=0
Dn Type=3
Dn Slope=0.005
Boundary for River Rch & Prof#=Stream0132,Reach-1,2
Up Type=0
Dn Type=3
Dn Slope=0.005
Boundary for River Rch & Prof#=Stream0132,Reach-1,3
Up Type=0
Dn Type=3
Dn Slope=0.005
Boundary for River Rch & Prof#=Stream0132,Reach-1,4
Up Type=0
Dn Type=3
Dn Slope=0.005
Boundary for River Rch & Prof#=Stream0132,Reach-1,5
Up Type=0
Dn Type=3
Dn Slope=0.005
Boundary for River Rch & Prof#=Stream0132,Reach-1,6
Up Type=0
Dn Type=3
Dn Slope=0.005
Boundary for River Rch & Prof#=Stream0132,Reach-1,7
Up Type=0
Dn Type=3
Dn Slope=0.005

--- Stream0132.g01 (geometry) ---

Geom Title=Existing Conditions

River Reach=Stream0132,Reach-1
Reach XY= 30
      1796675.00     13933525.00      1796781.22     13933532.74
      1796915.34     13933664.21      1796998.83     13933697.87
      1797033.05     13933781.41      1797080.85     13933823.46
      1797123.22     13933821.67      1797180.93     13933777.30
      1797314.49     13933773.77      1797380.98     13933727.36
      1797477.43     13933719.48      1797615.58     13933585.89
      1797669.38     13933569.38      1797688.73     13933512.02
      1797864.22     13933334.68      1797883.18     13933268.96
      1797964.20     13933184.67      1798071.45     13933023.53
      1798080.47     13932872.55      1798240.22     13932725.24
      1798331.17     13932732.76      1798535.44     13932923.96
      1798669.07     13932922.77      1798831.75     13932834.10
      1798919.17     13932922.67      1798931.14     13932977.17
      1798972.67     13933030.97      1798985.50     13933134.81
      1799072.46     13933219.70      1799125.00     13933225.00

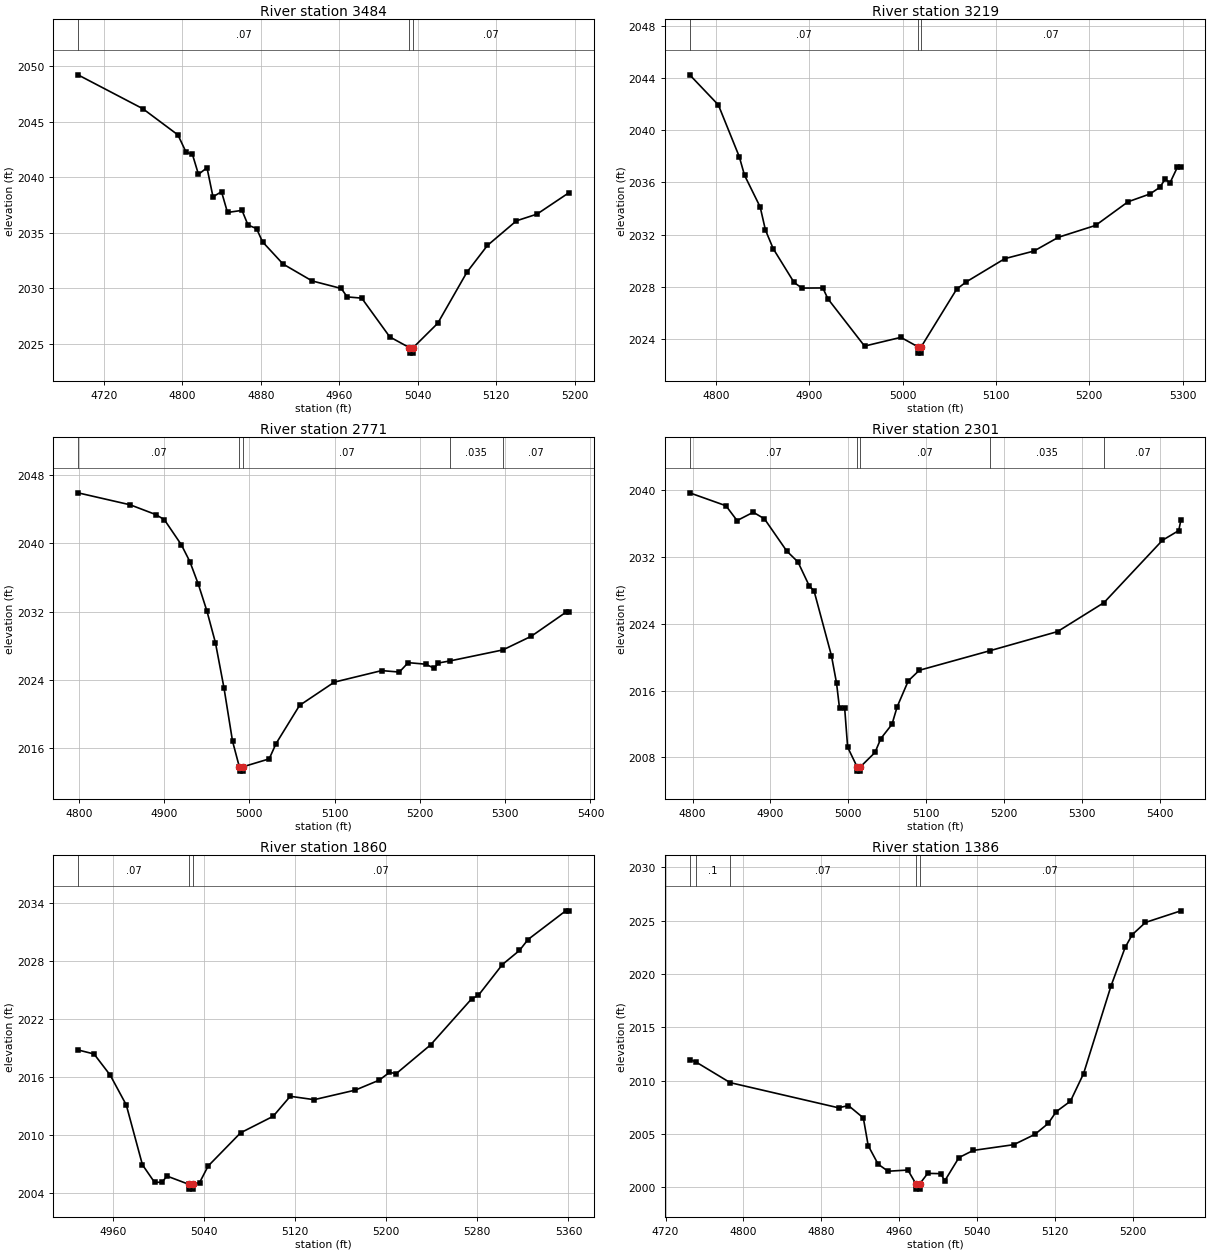
Type RM Length L Ch R = 1,3484,265,265,265
BEGIN DESCRIPTION:
Stream0132 8.0
END DESCRIPTION:
XS GIS Cut Line= 2
      1796542.66     13933775.07      1796830.45     13933365.46
#Sta/Elev= 30
  4693.7 2049.23  4759.8 2046.18  4795.6 2043.82  4803.8 2042.28  4810.4 2042.06
  4816.5 2040.27  4825.2 2040.87  4831.3 2038.25  4840.0 2038.71  4846.1 2036.84
  4860.9 2037.03  4867.0 2035.71  4875.7 2035.39  4881.8 2034.20  4902.7 2032.20
  4932.3 2030.68  4962.0 2030.00  4968.1 2029.24  4982.9 2029.13  5011.5 2025.64
  5031.4 2024.68  5031.7 2024.18  5035.2 2024.18  5035.4 2024.68  5060.4 2026.87
  5090.1 2031.46  5111.0 2033.87  5140.6 2036.09  5161.5 2036.69  5194.3 2038.63
#Mann=3,-1,0
  4693.7    0.07       0  5031.4    0.05       0  5035.4    0.07       0
Bank Sta=5031.4,5035.4
Exp/Cntr=0.3,0.1

Type RM Length L Ch R = 1,3219,448,448,448
BEGIN DESCRIPTION:
Stream0132 7.0
END DESCRIPTION:
XS GIS Cut Line= 3
      1796725.00     13933775.00      1796925.00     13933675.00
      1797004.21     13933383.06
#Sta/Elev= 30
  4772.0 2044.25  4802.7 2041.94  4825.1 2037.97  4830.7 2036.55  4847.5 2034.11
  4853.1 2032.35  4861.4 2030.92  4883.8 2028.32  4892.2 2027.89  4914.6 2027.90
  4920.1 2027.06  4959.3 2023.44  4998.2 2024.11  5016.1 2023.40  5016.4 2022.90
  5019.9 2022.90  5020.1 2023.40  5057.9 2027.80  5068.1 2028.36  5109.6 2030.15
  5140.7 2030.73  5167.0 2031.79  5206.8 2032.70  5241.5 2034.51  5265.0 2035.11
  5275.4 2035.61  5281.3 2036.24  5286.5 2035.97  5294.5 2037.18  5298.1 2037.18
#Mann=3,-1,0
  4772.0    0.07       0  5016.1    0.05       0  5020.1    0.07       0
Bank Sta=5016.1,5020.1
Exp/Cntr=0.3,0.1

Type RM Length L Ch R = 1,2771,470,470,470
BEGIN DESCRIPTION:
Stream0132 6.0
END DESCRIPTION:
XS GIS Cut Line= 3
      1797276.35     13933976.23      1797275.00     13933775.00
      1797181.78     13933412.11
#Sta/Elev= 30
  4799.1 2045.88  4860.3 2044.48  4890.3 2043.34  4900.3 2042.75  4920.3 2039.81
  4930.3 2037.84  4940.3 2035.17  4950.3 2032.06  4960.3 2028.35  4970.3 2023.08
  4980.3 2016.86  4988.3 2013.85  4988.6 2013.35  4992.1 2013.35  4992.3 2013.85
  5023.3 2014.78  5031.3 2016.56  5058.9 2021.03  5099.6 2023.75  5155.2 2025.10
  5175.9 2024.93  5186.3 2026.03  5206.8 2025.85  5216.7 2025.38  5221.8 2025.99
  5235.2 2026.23  5297.4 2027.52  5330.7 2029.12  5370.9 2031.90  5375.0 2031.90
#Mann=5,-1,0
  4799.1    0.07       0  4988.3    0.05       0  4992.3    0.07       0
  5235.2   0.035       0  5297.4    0.07       0
Bank Sta=4988.3,4992.3
Exp/Cntr=0.3,0.1

Type RM Length L Ch R = 1,2301,441,441,441
BEGIN DESCRIPTION:
Stream0132 5.0
END DESCRIPTION:
XS GIS Cut Line= 3
      1797800.02     13933725.37      1797675.00     13933575.00
      1797387.06     13933249.28
#Sta/Elev= 30
  4796.4 2039.72  4842.9 2038.17  4857.2 2036.39  4878.0 2037.39  4892.3 2036.60
  4921.0 2032.73  4935.3 2031.43  4949.6 2028.60  4956.1 2027.91  4978.3 2020.18
  4984.8 2016.92  4988.7 2013.85  4995.3 2013.85  4999.1 2009.20  5011.3 2006.83
  5011.5 2006.33  5015.0 2006.33  5015.3 2006.83  5034.2 2008.57  5041.7 2010.24
  5056.0 2011.95  5062.6 2014.04  5076.9 2017.16  5091.1 2018.43  5181.8 2020.78
  5268.4 2023.07  5328.1 2026.55  5403.1 2034.03  5424.0 2035.19  5426.7 2036.44
#Mann=5,-1,0
  4796.4    0.07       0  5011.3    0.05       0  5015.3    0.07       0
  5181.8   0.035       0  5328.1    0.07       0
Bank Sta=5011.3,5015.3
Exp/Cntr=0.3,0.1

Type RM Length L Ch R = 1,1860,474,474,474
BEGIN DESCRIPTION:
Stream0132 4.0
END DESCRIPTION:
XS GIS Cut Line= 3
      1797975.00     13933275.00      1797925.00     13933225.00
      1797624.97     13933024.98
#Sta/Elev= 30
  4929.3 2018.80  4943.4 2018.38  4957.6 2016.19  4971.7 2013.11  4985.9 2006.91
  4996.5 2005.10  5003.0 2005.10  5007.5 2005.74  5026.6 2004.89  5026.8 2004.39
  5030.3 2004.39  5030.6 2004.89  5036.1 2005.07  5043.6 2006.78  5072.1 2010.22
  5100.7 2011.93  5115.7 2014.00  5136.7 2013.65  5172.8 2014.64  5193.8 2015.67
  5202.8 2016.47  5208.8 2016.35  5238.9 2019.32  5274.9 2024.08  5280.9 2024.45
  5302.0 2027.64  5317.0 2029.10  5324.5 2030.23  5357.6 2033.20  5360.6 2033.20
#Mann=3,-1,0
  4929.3    0.07       0  5026.6    0.05       0  5030.6    0.07       0
Bank Sta=5026.6,5030.6
Exp/Cntr=0.3,0.1

Type RM Length L Ch R = 1,1386,420,420,420
BEGIN DESCRIPTION:
Stream0132 3.0
END DESCRIPTION:
XS GIS Cut Line= 3
      1798175.00     13933074.99      1798125.00     13932825.00
      1797925.03     13932675.02
#Sta/Elev= 30
  4744.8 2011.97  4751.2 2011.74  4786.4 2009.80  4897.8 2007.44  4908.0 2007.65
  4923.3 2006.49  4928.3 2003.89  4938.5 2002.15  4948.7 2001.49  4969.1 2001.60
  4977.3 2000.31  4977.6 1999.81  4981.1 1999.81  4981.3 2000.31  4989.5 2001.29
  5002.9 2001.26  5007.0 2000.59  5021.6 2002.77  5036.2 2003.44  5077.9 2003.98
  5099.7 2004.95  5113.3 2005.97  5121.6 2007.08  5136.2 2008.06  5149.7 2010.65
  5177.9 2018.87  5192.4 2022.48  5199.7 2023.68  5213.3 2024.83  5249.7 2025.92
#Mann=5,-1,0
  4744.8    0.07       0  4751.2     0.1       0  4786.4    0.07       0
  4977.3    0.05       0  4981.3    0.07       0
Bank Sta=4977.3,4981.3
Exp/Cntr=0.3,0.1

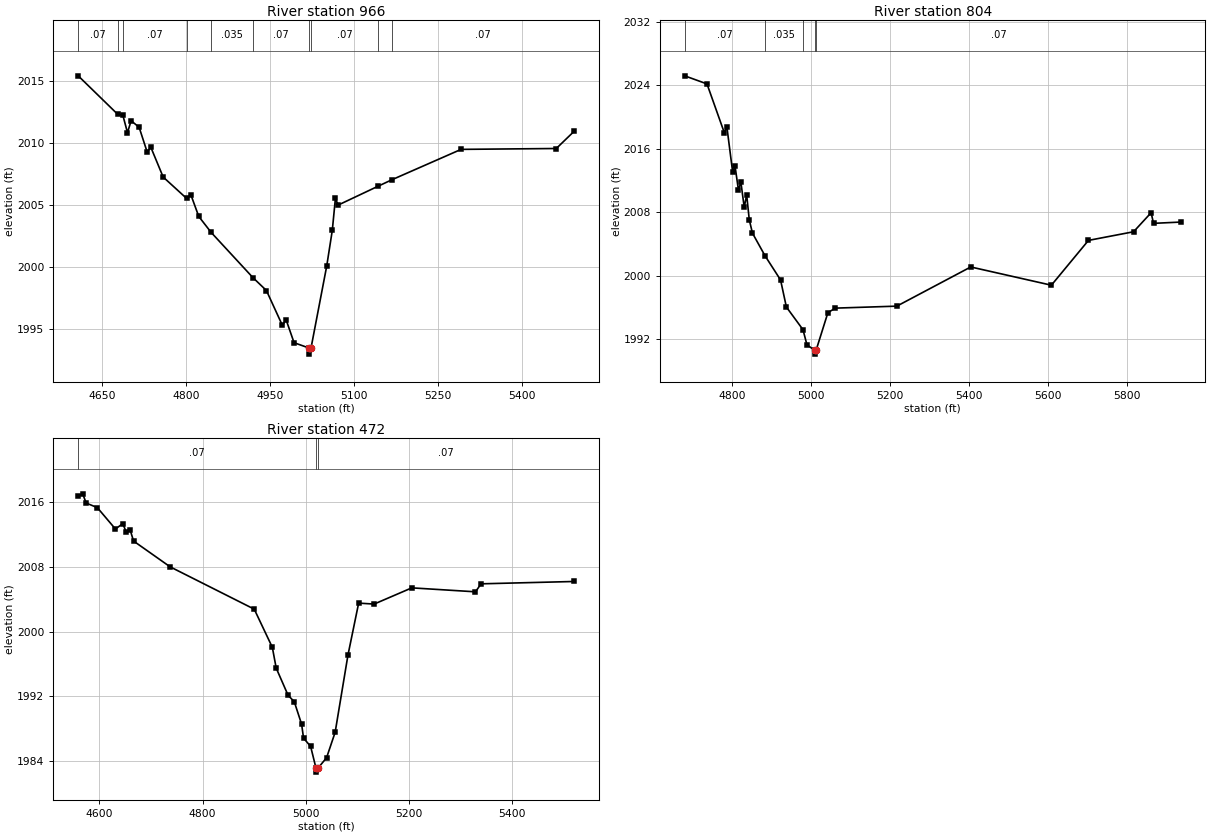
Type RM Length L Ch R = 1,966,162,162,162
BEGIN DESCRIPTION:
Stream0132 2.0
END DESCRIPTION:
XS GIS Cut Line= 3
      1798199.66     13933153.13      1798459.20     13932848.88
      1798465.66     13932363.13
#Sta/Elev= 30
  4607.5 2015.44  4678.2 2012.33  4687.0 2012.30  4695.5 2010.86  4702.0 2011.82
  4716.3 2011.29  4730.6 2009.30  4737.2 2009.68  4759.2 2007.28  4801.2 2005.55
  4808.6 2005.86  4822.8 2004.10  4845.0 2002.81  4919.5 1999.17  4943.6 1998.13
  4972.2 1995.31  4978.7 1995.78  4993.0 1993.92  5019.3 1993.50  5019.5 1993.00
  5023.3 1993.50  5051.3 2000.10  5061.3 2002.99  5066.8 2005.55  5071.8 2005.02
  5142.6 2006.53  5168.2 2007.07  5291.3 2009.51  5461.3 2009.58  5493.2 2010.97
#Mann=10,-1,0
  4607.5    0.07       0  4678.2     0.1       0  4687.0    0.07       0
  4801.2     0.1       0  4845.0   0.035       0  4919.5    0.07       0
  5019.3    0.05       0  5023.3    0.07       0  5142.6     0.1       0
  5168.2    0.07       0
Bank Sta=5019.3,5023.3
Exp/Cntr=0.3,0.1

Type RM Length L Ch R = 1,804,332,332,332
BEGIN DESCRIPTION:
Stream0132 1.1
END DESCRIPTION:
XS GIS Cut Line= 4
      1798407.57     13933186.71      1798580.04     13932951.38
      1798753.91     13932449.46      1799104.72     13932199.49
#Sta/Elev= 30
  4680.8 2025.18  4737.2 2024.16  4781.2 2017.98  4787.4 2018.77  4802.0 2013.08
  4808.2 2013.76  4816.7 2010.79  4822.9 2011.77  4831.3 2008.61  4837.5 2010.16
  4844.1 2007.02  4852.2 2005.34  4883.8 2002.50  4923.2 1999.44  4937.9 1996.03
  4979.9 1993.17  4989.9 1991.26  5009.1 1990.59  5009.3 1990.09  5013.1 1990.59
  5042.8 1995.31  5061.4 1995.89  5217.1 1996.14  5404.0 2001.08  5607.8 1998.78
  5701.5 2004.43  5815.6 2005.52  5859.9 2007.92  5866.0 2006.58  5934.5 2006.74
#Mann=5,-1,0
  4680.8    0.07       0  4883.8   0.035       0  4979.9    0.07       0
  5009.1    0.05       0  5013.1    0.07       0
Bank Sta=5009.1,5013.1
Exp/Cntr=0.3,0.1

Type RM Length L Ch R = 1,472,0,0,0
BEGIN DESCRIPTION:
Stream0132 1.0
END DESCRIPTION:
XS GIS Cut Line= 3
      1798582.61     13933204.67      1798875.00     13932875.00
      1799007.47     13932370.35
#Sta/Elev= 30
  4558.7 2016.83  4567.4 2017.07  4574.1 2015.93  4595.8 2015.36  4630.9 2012.71
  4645.2 2013.38  4651.9 2012.32  4659.4 2012.62  4666.1 2011.22  4737.2 2008.02
  4900.3 2002.78  4935.4 1998.05  4942.9 1995.48  4965.9 1992.12  4978.0 1991.31
  4992.2 1988.53  4996.0 1986.80  5009.7 1985.78  5020.1 1983.09  5020.4 1982.59
  5024.1 1983.09  5040.7 1984.38  5057.3 1987.53  5082.1 1997.07  5102.9 2003.53
  5132.9 2003.41  5206.1 2005.42  5329.6 2004.93  5340.5 2005.92  5521.1 2006.21
#Mann=3,-1,0
  4558.7    0.07       0  5020.1    0.05       0  5024.1    0.07       0
Bank Sta=5020.1,5024.1
Exp/Cntr=0.3,0.1

Chan Stop Cuts=-1