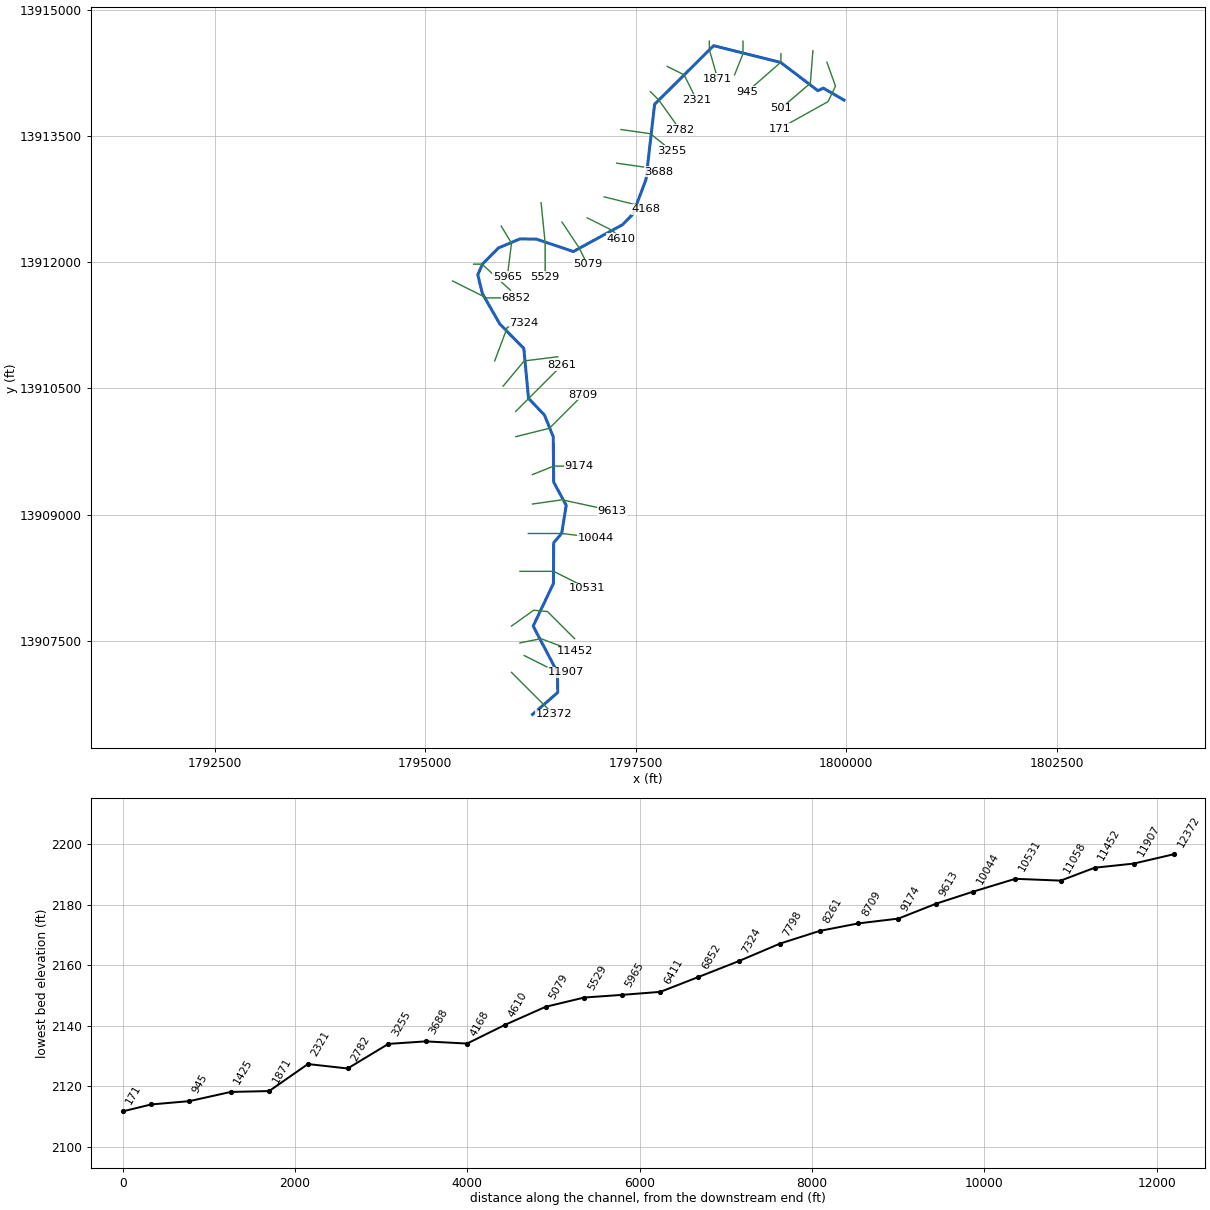
--- Stream0137.prj (project) ---

Proj Title=Stream0137 Base Level Engineering
Current Plan=p01
Default Exp/Contr=0.3,0.1
English Units
Geom File=g01
Flow File=f01
Plan File=p01
BEGIN DESCRIPTION:
Stream0137
END DESCRIPTION:

--- Stream0137.p01 (plan) ---

Plan Title=Multiple Run
Short Identifier=Multiple
Geom File=g01
Flow File=f01
Subcritical Flow
K Sum by GR= 0
Std Step Tol= 0.01
Critical Tol= 0.01
Num of Std Step Trials= 20
Max Error Tol= 0.3
Flow Tol Ratio= 0.001
Split Flow NTrial= 30
Split Flow Tol= 0.02
Split Flow Ratio= 0.02
Log Output Level= 0
Friction Slope Method= 1
Unsteady Friction Slope Method= 2
Unsteady Bridges Friction Slope Method= 1
Parabolic Critical Depth
Global Vel Dist=  1 , 1 , 1
Global Log Level= 0
CheckData=True
Encroach Param= -1, 0, 0, 0
BEGIN DESCRIPTION:
Multiple Run
END DESCRIPTION:

--- Stream0137.f01 (steady flow) ---

Flow Title=Multiple
Number of Profiles=7
Profile Names=10-year,25-year,50-year,1pct_min,100-year,1pct_plu,500-year
River Rch & RM= Stream0137,Reach-1,12372
    1372    2365    3315    2241    4471    8921    8053
River Rch & RM= Stream0137,Reach-1,6852
    1841    3225    4570    3120    6225   12420   11438
River Rch & RM= Stream0137,Reach-1,5529
    1996    3507    4979    3404    6791   13550   12511
River Rch & RM= Stream0137,Reach-1,5079
    2234    3941    5608    3841    7664   15292   14175
Boundary for River Rch & Prof#=Stream0137,Reach-1,1
Up Type=0
Dn Type=3
Dn Slope=0.005
Boundary for River Rch & Prof#=Stream0137,Reach-1,2
Up Type=0
Dn Type=3
Dn Slope=0.005
Boundary for River Rch & Prof#=Stream0137,Reach-1,3
Up Type=0
Dn Type=3
Dn Slope=0.005
Boundary for River Rch & Prof#=Stream0137,Reach-1,4
Up Type=0
Dn Type=3
Dn Slope=0.005
Boundary for River Rch & Prof#=Stream0137,Reach-1,5
Up Type=0
Dn Type=3
Dn Slope=0.005
Boundary for River Rch & Prof#=Stream0137,Reach-1,6
Up Type=0
Dn Type=3
Dn Slope=0.005
Boundary for River Rch & Prof#=Stream0137,Reach-1,7
Up Type=0
Dn Type=3
Dn Slope=0.005

--- Stream0137.g01 (geometry) ---

Geom Title=Existing Conditions

River Reach=Stream0137,Reach-1
Reach XY= 30
      1796275.00     13906625.00      1796573.95     13906885.43
      1796571.25     13907123.45      1796282.32     13907674.90
      1796522.94     13908180.86      1796526.06     13908664.56
      1796621.38     13908776.50      1796674.48     13909109.78
      1796526.06     13909385.44      1796521.25     13909923.45
      1796417.14     13910181.17      1796227.06     13910380.85
      1796171.25     13910973.45      1795885.63     13911265.00
      1795678.76     13911626.56      1795624.59     13911850.00
      1795680.83     13911977.30      1795868.83     13912167.14
      1796125.00     13912275.00      1796319.07     13912272.75
      1796759.61     13912125.09      1797345.09     13912444.79
      1797469.17     13912572.70      1797622.73     13912980.94
      1797725.00     13913875.00      1798426.58     13914571.33
      1799223.50     13914371.38      1799665.01     13914036.26
      1799728.33     13914066.98      1799975.00     13913925.00

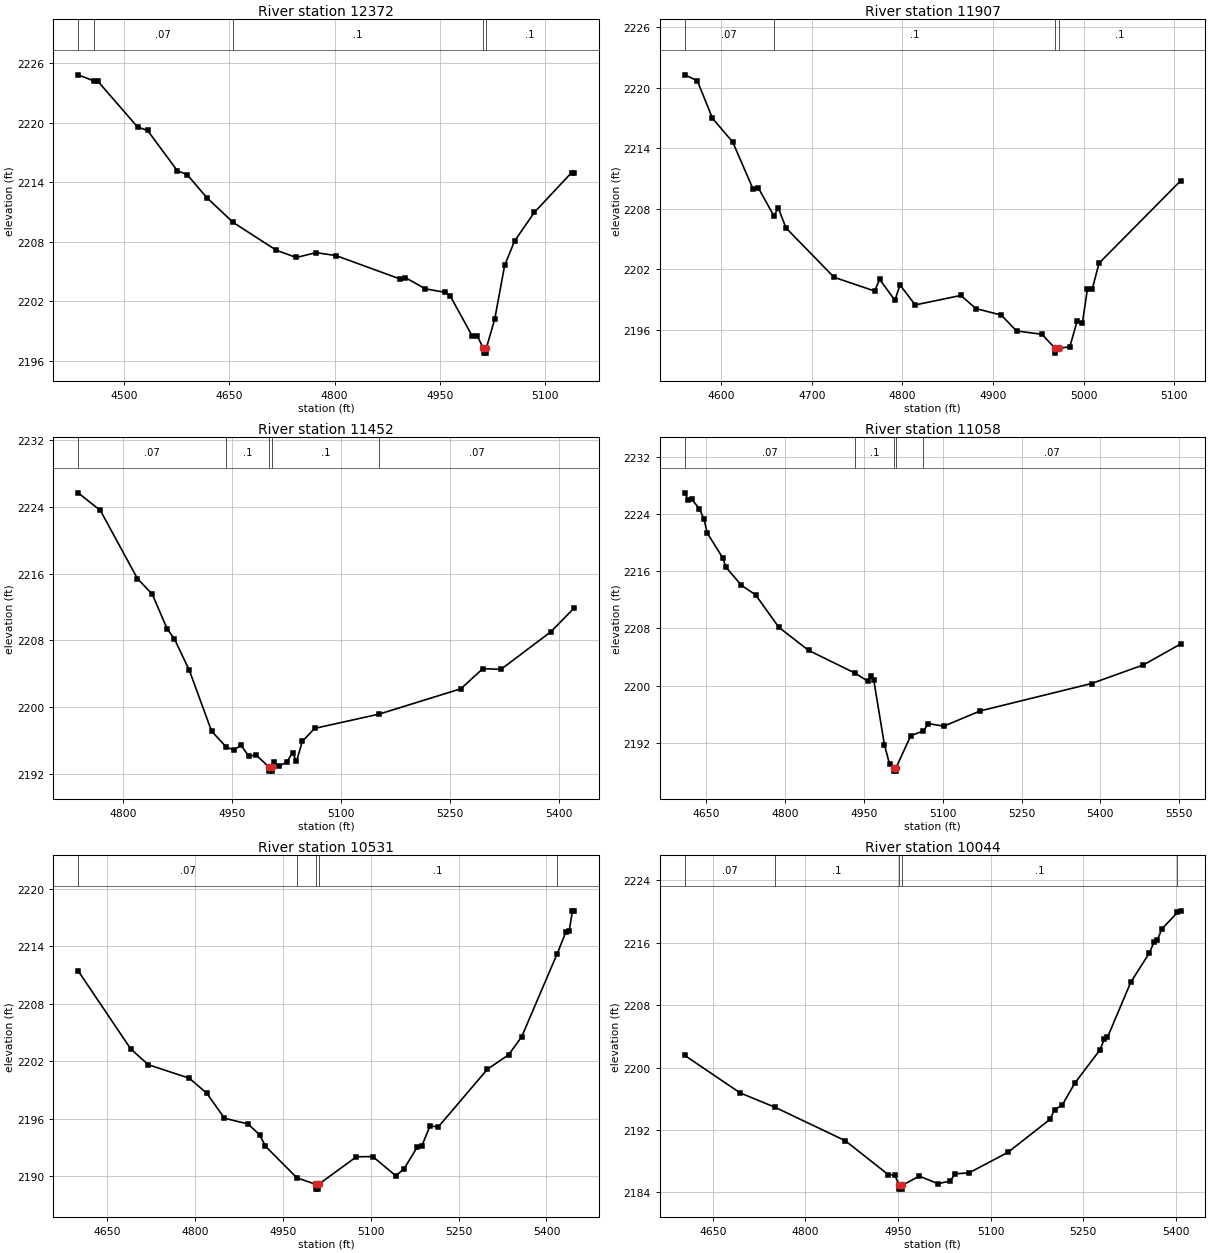
Type RM Length L Ch R = 1,12372,465,465,465
BEGIN DESCRIPTION:
Stream0137 27.0
END DESCRIPTION:
XS GIS Cut Line= 3
      1796025.01     13907124.99      1796425.00     13906725.00
      1796525.01     13906624.99
#Sta/Elev= 30
  4434.3 2224.83  4456.3 2224.23  4462.6 2224.17  4519.1 2219.57  4533.3 2219.23
  4575.7 2215.17  4589.8 2214.77  4618.1 2212.43  4655.2 2209.96  4717.1 2207.14
  4745.4 2206.42  4773.7 2206.91  4802.0 2206.61  4893.9 2204.24  4901.0 2204.39
  4929.3 2203.26  4957.5 2202.91  4964.6 2202.57  4996.4 2198.48  5003.5 2198.48
  5012.0 2197.28  5012.3 2196.78  5016.0 2196.78  5016.3 2197.28  5028.3 2200.22
  5042.4 2205.62  5056.5 2208.07  5084.8 2210.97  5137.9 2214.98  5141.4 2214.98
#Mann=5,-1,0
  4434.3     0.1       0  4456.3    0.07       0  4655.2     0.1       0
  5012.0    0.05       0  5016.3     0.1       0
Bank Sta=5012,5016.3
Exp/Cntr=0.3,0.1

Type RM Length L Ch R = 1,11907,455,455,455
BEGIN DESCRIPTION:
Stream0137 26.0
END DESCRIPTION:
XS GIS Cut Line= 3
      1796175.00     13907325.00      1796575.00     13907125.00
      1796674.99     13907125.00
#Sta/Elev= 30
  4559.7 2221.29  4573.7 2220.71  4590.4 2216.98  4612.8 2214.62  4635.2 2209.96
  4640.8 2210.11  4658.1 2207.32  4663.1 2208.07  4671.5 2206.11  4724.6 2201.21
  4769.3 2199.85  4774.9 2201.00  4791.7 2198.93  4797.3 2200.46  4814.1 2198.47
  4864.4 2199.41  4881.1 2198.11  4909.1 2197.46  4925.9 2195.89  4953.8 2195.56
  4968.2 2194.19  4968.5 2193.69  4972.9 2194.19  4984.6 2194.31  4992.9 2196.90
  4998.5 2196.67  5004.1 2200.05  5009.4 2200.05  5016.9 2202.61  5106.9 2210.78
#Mann=4,-1,0
  4559.7    0.07       0  4658.1     0.1       0  4968.2    0.05       0
  4972.9     0.1       0
Bank Sta=4968.2,4972.9
Exp/Cntr=0.3,0.1

Type RM Length L Ch R = 1,11452,394,394,394
BEGIN DESCRIPTION:
Stream0137 25.0
END DESCRIPTION:
XS GIS Cut Line= 3
      1796124.96     13907474.99      1796375.00     13907525.00
      1796775.01     13907375.00
#Sta/Elev= 30
  4738.4 2225.71  4769.0 2223.60  4820.0 2215.42  4840.4 2213.54  4860.8 2209.41
  4871.0 2208.15  4891.4 2204.41  4922.0 2197.11  4942.4 2195.18  4952.6 2194.86
  4962.8 2195.40  4973.0 2194.10  4983.2 2194.25  5000.8 2192.81  5001.1 2192.31
  5005.2 2192.31  5005.6 2192.81  5008.5 2193.36  5014.8 2192.91  5025.4 2193.39
  5033.4 2194.52  5038.8 2193.48  5046.8 2195.88  5063.7 2197.44  5152.3 2199.15
  5264.8 2202.19  5295.1 2204.61  5320.0 2204.52  5388.6 2209.03  5420.6 2211.88
#Mann=5,-1,0
  4738.4    0.07       0  4942.4     0.1       0  5000.8    0.05       0
  5005.6     0.1       0  5152.3    0.07       0
Bank Sta=5000.8,5005.6
Exp/Cntr=0.3,0.1

Type RM Length L Ch R = 1,11058,527,527,527
BEGIN DESCRIPTION:
Stream0137 24.0
END DESCRIPTION:
XS GIS Cut Line= 4
      1796025.03     13907675.02      1796287.81     13907862.72
      1796452.32     13907847.68      1796775.03     13907524.97
#Sta/Elev= 30
  4608.4 2226.94  4615.7 2225.90  4621.9 2226.03  4636.6 2224.72  4645.2 2223.28
  4651.4 2221.34  4680.9 2217.85  4687.0 2216.56  4716.5 2214.02  4743.5 2212.69
  4787.8 2208.15  4844.3 2204.93  4933.3 2201.73  4957.4 2200.60  4962.4 2201.28
  4968.7 2200.72  4988.8 2191.75  4998.8 2189.00  5006.4 2188.55  5006.8 2188.05
  5010.9 2188.05  5011.2 2188.55  5039.0 2193.00  5063.1 2193.67  5072.6 2194.69
  5102.0 2194.33  5171.0 2196.46  5383.2 2200.29  5482.2 2202.90  5552.9 2205.81
#Mann=5,-1,0
  4608.4    0.07       0  4933.3     0.1       0  5006.4    0.05       0
  5011.2     0.1       0  5063.1    0.07       0
Bank Sta=5006.4,5011.2
Exp/Cntr=0.3,0.1

Type RM Length L Ch R = 1,10531,487,487,487
BEGIN DESCRIPTION:
Stream0137 23.0
END DESCRIPTION:
XS GIS Cut Line= 3
      1796125.03     13908325.00      1796525.00     13908325.00
      1796925.01     13908124.99
#Sta/Elev= 30
  4600.0 2211.45  4690.0 2203.28  4720.0 2201.64  4790.0 2200.23  4820.0 2198.65
  4850.0 2196.05  4890.0 2195.46  4910.0 2194.33  4920.0 2193.13  4973.7 2189.83
  5005.9 2189.15  5006.2 2188.65  5010.5 2188.65  5010.9 2189.15  5075.4 2192.03
  5103.4 2192.05  5142.5 2190.05  5156.5 2190.74  5178.9 2193.00  5187.2 2193.17
  5201.2 2195.26  5215.2 2195.14  5299.0 2201.16  5335.4 2202.68  5357.7 2204.56
  5418.3 2213.23  5433.2 2215.50  5438.8 2215.60  5444.4 2217.71  5447.2 2217.71
#Mann=5,-1,0
  4600.0    0.07       0  4973.7     0.1       0  5005.9    0.05       0
  5010.9     0.1       0  5418.3    0.07       0
Bank Sta=5005.9,5010.9
Exp/Cntr=0.3,0.1

Type RM Length L Ch R = 1,10044,431,431,431
BEGIN DESCRIPTION:
Stream0137 22.0
END DESCRIPTION:
XS GIS Cut Line= 3
      1796225.04     13908775.00      1796625.00     13908775.00
      1797025.03     13908725.00
#Sta/Elev= 30
  4604.4 2201.57  4694.4 2196.75  4751.1 2194.90  4864.4 2190.63  4934.4 2186.26
  4944.4 2186.26  4951.8 2184.92  4952.2 2184.42  4956.5 2184.42  4956.9 2184.92
  4984.4 2186.09  5014.4 2185.12  5034.6 2185.45  5042.1 2186.38  5064.8 2186.50
  5127.8 2189.13  5195.8 2193.35  5203.4 2194.58  5216.0 2195.22  5236.1 2198.00
  5276.5 2202.22  5284.0 2203.63  5289.1 2203.88  5326.8 2210.94  5357.1 2214.71
  5364.6 2216.13  5369.7 2216.34  5377.2 2217.77  5402.3 2219.88  5407.5 2220.09
#Mann=5,-1,0
  4604.4    0.07       0  4751.1     0.1       0  4951.8    0.05       0
  4956.9     0.1       0  5402.3    0.07       0
Bank Sta=4951.8,4956.9
Exp/Cntr=0.3,0.1

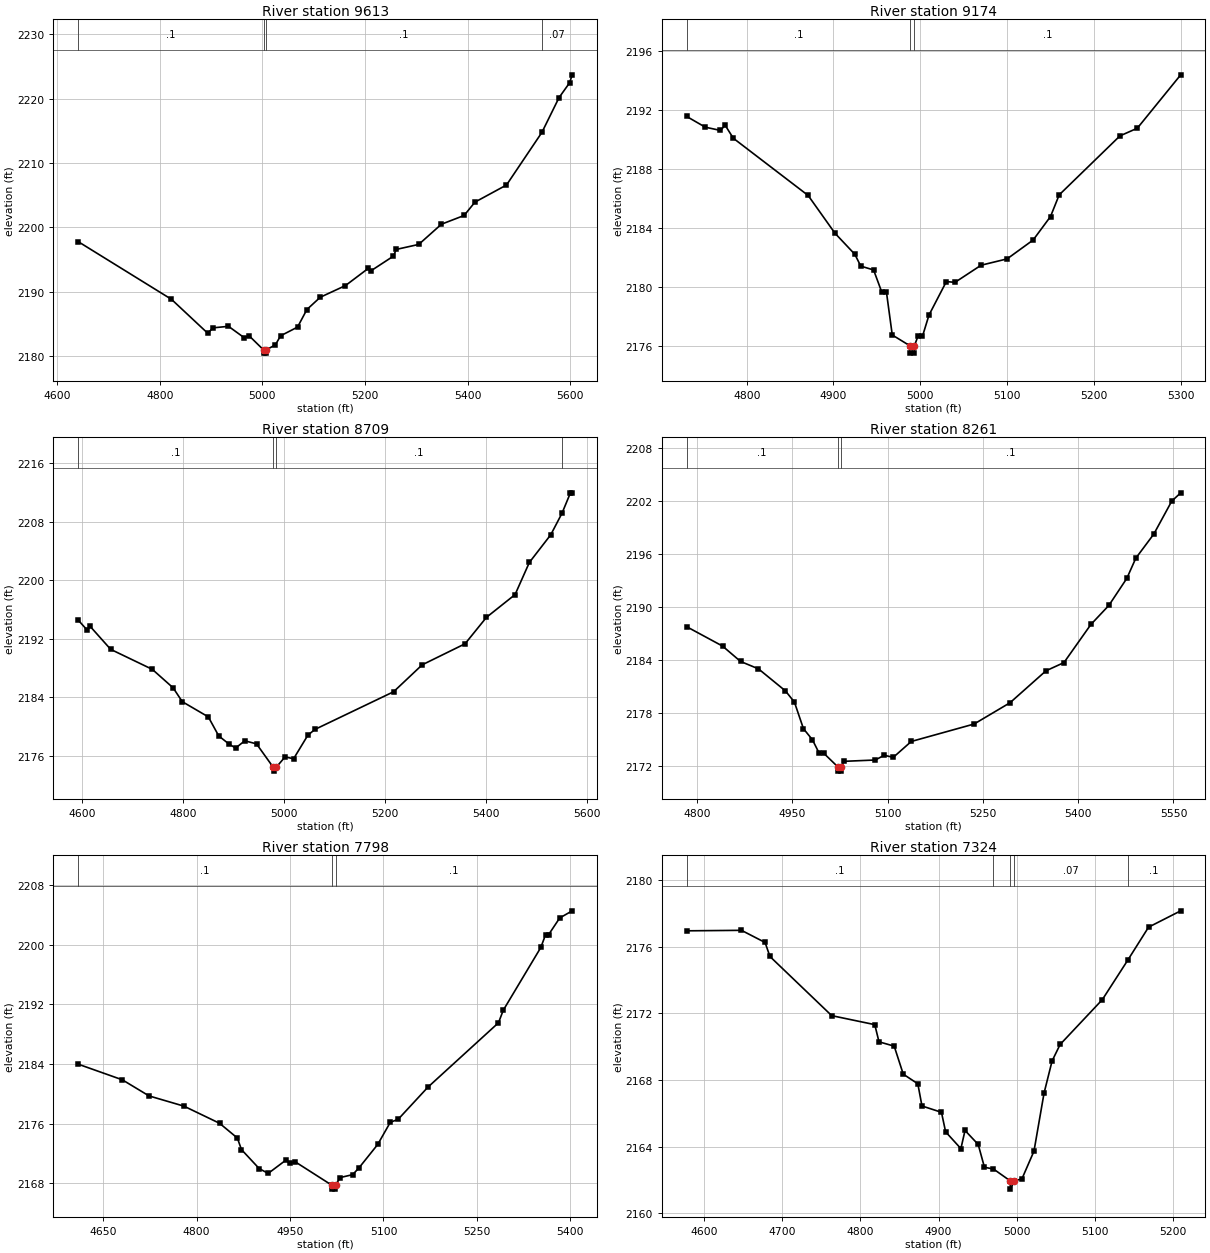
Type RM Length L Ch R = 1,9613,439,439,439
BEGIN DESCRIPTION:
Stream0137 21.0
END DESCRIPTION:
XS GIS Cut Line= 3
      1796275.00     13909125.00      1796625.00     13909175.00
      1797220.11     13909046.44
#Sta/Elev= 30
  4641.1 2197.78  4822.9 2188.80  4893.6 2183.52  4903.7 2184.36  4934.0 2184.60
  4964.4 2182.84  4974.5 2183.10  5002.3 2180.93  5002.7 2180.43  5007.0 2180.43
  5007.4 2180.93  5025.3 2181.72  5035.6 2183.13  5068.5 2184.48  5086.7 2187.21
  5112.7 2189.12  5161.9 2190.94  5206.1 2193.60  5211.2 2193.22  5255.3 2195.52
  5260.7 2196.56  5304.6 2197.34  5348.7 2200.48  5392.9 2201.84  5414.1 2203.92
  5475.5 2206.58  5544.5 2214.77  5577.8 2220.17  5598.3 2222.47  5603.5 2223.72
#Mann=4,-1,0
  4641.1     0.1       0  5002.3    0.05       0  5007.4     0.1       0
  5544.5    0.07       0
Bank Sta=5002.3,5007.4
Exp/Cntr=0.3,0.1

Type RM Length L Ch R = 1,9174,465,465,465
BEGIN DESCRIPTION:
Stream0137 20.0
END DESCRIPTION:
XS GIS Cut Line= 3
      1796275.03     13909475.01      1796525.00     13909575.00
      1796824.98     13909575.00
#Sta/Elev= 30
  4730.8 2191.54  4752.3 2190.81  4769.8 2190.59  4775.2 2190.94  4784.6 2190.06
  4870.8 2186.18  4901.7 2183.62  4924.6 2182.19  4931.4 2181.39  4946.2 2181.13
  4955.6 2179.63  4961.0 2179.63  4967.7 2176.72  4988.0 2175.99  4988.4 2175.49
  4992.8 2175.49  4993.2 2175.99  4997.3 2176.63  5002.5 2176.63  5010.0 2178.07
  5030.0 2180.34  5040.0 2180.29  5070.0 2181.45  5100.0 2181.88  5130.0 2183.16
  5150.0 2184.75  5160.0 2186.22  5230.0 2190.22  5250.0 2190.74  5300.0 2194.36
#Mann=3,-1,0
  4730.8     0.1       0  4988.0    0.05       0  4993.2     0.1       0
Bank Sta=4988,4993.2
Exp/Cntr=0.3,0.1

Type RM Length L Ch R = 1,8709,448,448,448
BEGIN DESCRIPTION:
Stream0137 19.0
END DESCRIPTION:
XS GIS Cut Line= 3
      1796074.99     13909925.00      1796475.00     13910025.00
      1796874.99     13910424.99
#Sta/Elev= 30
  4592.3 2194.57  4610.4 2193.18  4615.5 2193.75  4656.7 2190.56  4739.2 2187.82
  4780.4 2185.29  4798.5 2183.40  4850.0 2181.32  4870.6 2178.72  4891.2 2177.59
  4904.1 2177.06  4922.2 2178.05  4945.4 2177.63  4978.8 2174.40  4979.2 2173.90
  4984.1 2174.40  5002.0 2175.85  5018.8 2175.59  5047.1 2178.82  5061.2 2179.61
  5216.8 2184.76  5273.3 2188.44  5358.2 2191.32  5400.6 2194.94  5457.2 2198.05
  5485.5 2202.45  5527.9 2206.24  5550.1 2209.18  5566.8 2211.97  5570.3 2211.97
#Mann=4,-1,0
  4592.3     0.1       0  4978.8    0.05       0  4984.1     0.1       0
  5550.1    0.07       0
Bank Sta=4978.8,4984.1
Exp/Cntr=0.3,0.1

Type RM Length L Ch R = 1,8261,463,463,463
BEGIN DESCRIPTION:
Stream0137 18.0
END DESCRIPTION:
XS GIS Cut Line= 3
      1796075.00     13910225.00      1796225.00     13910375.00
      1796624.98     13910774.98
#Sta/Elev= 30
  4783.6 2187.79  4840.2 2185.59  4868.5 2183.85  4896.7 2183.01  4939.2 2180.51
  4953.3 2179.24  4967.5 2176.23  4981.6 2174.98  4992.2 2173.46  4999.3 2173.46
  5021.4 2171.92  5021.8 2171.42  5026.3 2171.42  5026.7 2171.92  5031.1 2172.53
  5080.6 2172.68  5094.7 2173.22  5108.9 2172.98  5137.2 2174.78  5236.2 2176.76
  5292.7 2179.17  5349.3 2182.79  5377.6 2183.72  5420.0 2188.04  5448.3 2190.20
  5476.6 2193.27  5490.7 2195.55  5519.0 2198.28  5547.3 2202.02  5561.4 2202.96
#Mann=3,-1,0
  4783.6     0.1       0  5021.4    0.05       0  5026.7     0.1       0
Bank Sta=5021.4,5026.7
Exp/Cntr=0.3,0.1

Type RM Length L Ch R = 1,7798,474,474,474
BEGIN DESCRIPTION:
Stream0137 17.0
END DESCRIPTION:
XS GIS Cut Line= 3
      1795925.00     13910524.99      1796175.00     13910825.00
      1796574.97     13910875.00
#Sta/Elev= 30
  4609.6 2183.96  4680.6 2181.86  4723.5 2179.70  4779.5 2178.33  4836.8 2176.03
  4865.4 2174.05  4871.9 2172.51  4900.5 2169.95  4914.9 2169.31  4943.5 2171.10
  4950.0 2170.64  4957.8 2170.89  5017.6 2167.70  5018.0 2167.20  5022.5 2167.20
  5023.0 2167.70  5030.4 2168.75  5050.5 2169.14  5060.6 2170.04  5090.8 2173.19
  5111.0 2176.16  5123.6 2176.56  5171.4 2180.87  5284.8 2189.51  5292.4 2191.18
  5352.8 2199.61  5360.4 2201.32  5365.4 2201.34  5383.1 2203.56  5403.2 2204.52
#Mann=3,-1,0
  4609.6     0.1       0  5017.6    0.05       0  5023.0     0.1       0
Bank Sta=5017.6,5023
Exp/Cntr=0.3,0.1

Type RM Length L Ch R = 1,7324,472,472,472
BEGIN DESCRIPTION:
Stream0137 16.0
END DESCRIPTION:
XS GIS Cut Line= 3
      1795824.99     13910824.97      1795975.00     13911225.00
      1796175.01     13911275.00
#Sta/Elev= 30
  4577.1 2176.95  4647.4 2176.98  4677.7 2176.25  4683.9 2175.41  4763.1 2171.86
  4818.3 2171.32  4823.7 2170.29  4843.2 2170.03  4854.8 2168.35  4873.5 2167.77
  4878.8 2166.44  4903.8 2166.06  4909.1 2164.89  4928.7 2163.88  4934.0 2164.97
  4950.9 2164.13  4958.9 2162.76  4970.4 2162.66  4991.8 2161.95  4992.2 2161.45
  4997.2 2161.95  5006.9 2162.06  5022.4 2163.73  5035.3 2167.21  5045.6 2169.14
  5055.9 2170.13  5110.0 2172.82  5142.5 2175.18  5169.3 2177.17  5210.5 2178.15
#Mann=5,-1,0
  4577.1     0.1       0  4970.4    0.07       0  4991.8    0.05       0
  4997.2    0.07       0  5142.5     0.1       0
Bank Sta=4991.8,4997.2
Exp/Cntr=0.3,0.1

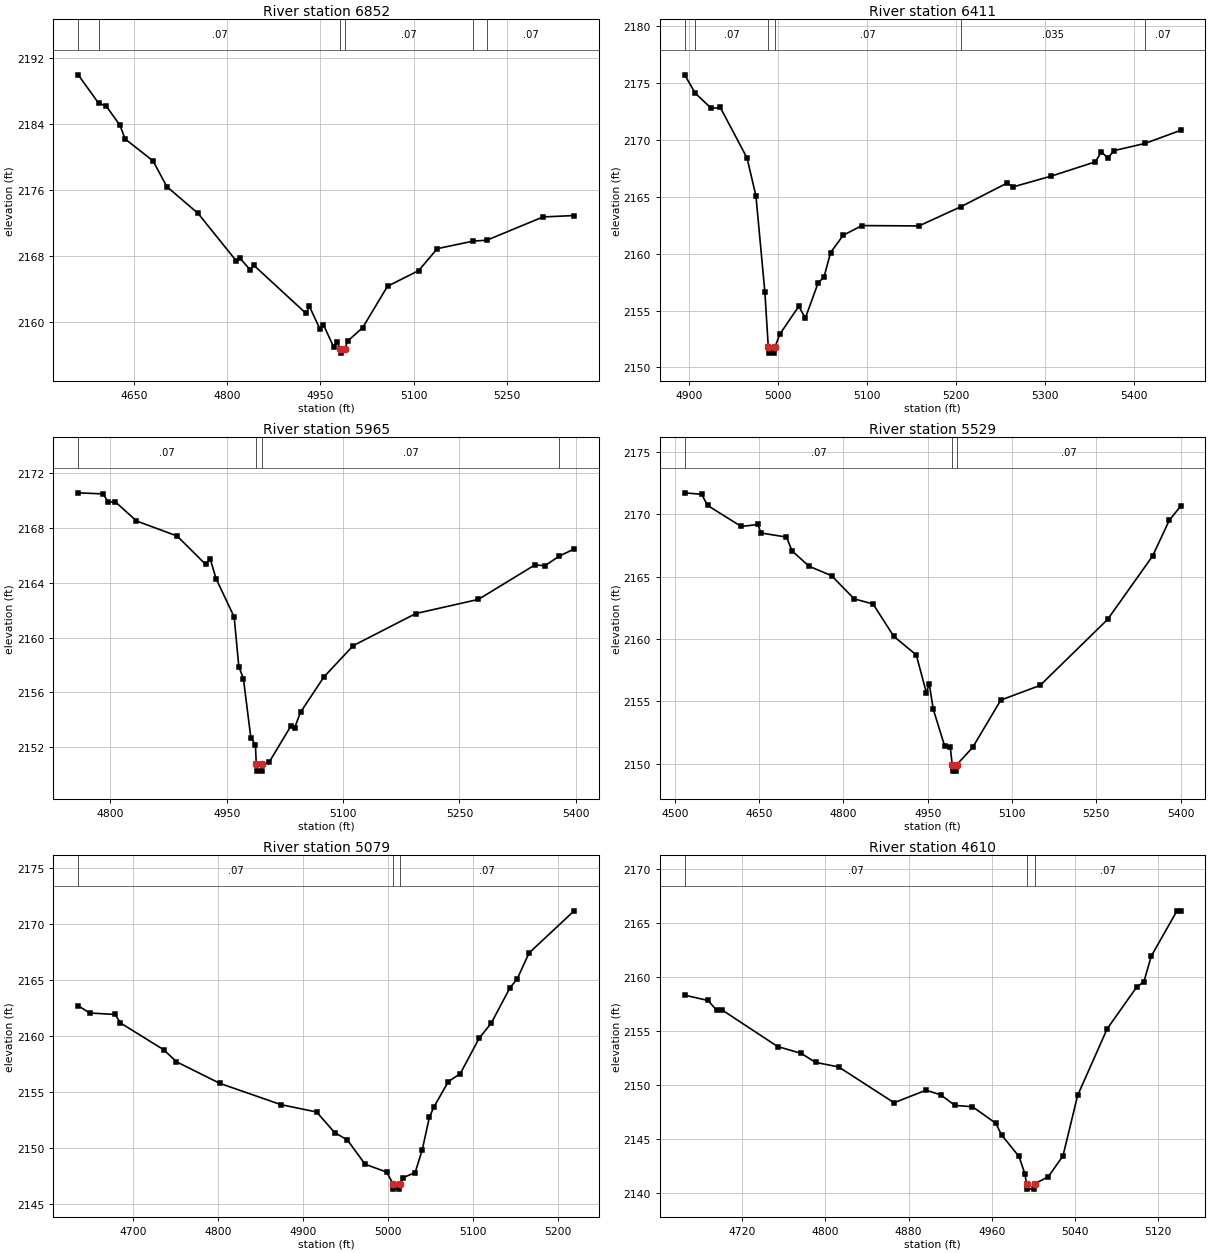
Type RM Length L Ch R = 1,6852,441,441,441
BEGIN DESCRIPTION:
Stream0137 15.0
END DESCRIPTION:
XS GIS Cut Line= 3
      1795325.02     13911774.99      1795725.00     13911575.00
      1796075.01     13911575.00
#Sta/Elev= 30
  4560.6 2189.96  4593.4 2186.51  4605.3 2186.20  4627.7 2183.83  4636.0 2182.17
  4680.8 2179.51  4703.1 2176.38  4753.4 2173.12  4814.9 2167.34  4820.5 2167.69
  4837.3 2166.26  4842.9 2166.83  4926.7 2160.99  4932.3 2161.83  4949.1 2159.10
  4954.7 2159.62  4971.5 2156.86  4977.0 2157.49  4981.8 2156.66  4982.3 2156.16
  4989.0 2156.66  4993.8 2157.63  5017.8 2159.25  5057.8 2164.28  5107.8 2166.18
  5137.8 2168.85  5195.8 2169.77  5217.3 2169.87  5307.8 2172.70  5357.8 2172.87
#Mann=6,-1,0
  4560.6     0.1       0  4593.4    0.07       0  4981.8    0.05       0
  4989.0    0.07       0  5195.8   0.035       0  5217.3    0.07       0
Bank Sta=4981.8,4989
Exp/Cntr=0.3,0.1

Type RM Length L Ch R = 1,6411,446,446,446
BEGIN DESCRIPTION:
Stream0137 14.0
END DESCRIPTION:
XS GIS Cut Line= 3
      1795574.97     13911975.00      1795675.00     13911975.00
      1796011.28     13911665.88
#Sta/Elev= 30
  4895.3 2175.72  4907.2 2174.10  4925.3 2172.77  4935.3 2172.85  4965.3 2168.41
  4975.3 2165.08  4985.3 2156.66  4989.2 2151.76  4989.7 2151.26  4995.9 2151.26
  4996.4 2151.76  5002.4 2152.96  5023.4 2155.37  5030.8 2154.34  5045.0 2157.41
  5051.8 2157.96  5059.1 2160.10  5073.3 2161.62  5094.3 2162.47  5158.3 2162.44
  5205.7 2164.14  5257.1 2166.20  5264.4 2165.88  5307.0 2166.82  5356.3 2168.07
  5363.1 2168.94  5370.5 2168.41  5377.3 2169.06  5412.1 2169.69  5452.1 2170.84
#Mann=6,-1,0
  4895.3     0.1       0  4907.2    0.07       0  4989.2    0.05       0
  4996.4    0.07       0  5205.7   0.035       0  5412.1    0.07       0
Bank Sta=4989.2,4996.4
Exp/Cntr=0.3,0.1

Type RM Length L Ch R = 1,5965,436,436,436
BEGIN DESCRIPTION:
Stream0137 13.0
END DESCRIPTION:
XS GIS Cut Line= 3
      1795902.76     13912427.01      1796025.00     13912225.00
      1795975.00     13911825.03
#Sta/Elev= 30
  4758.6 2170.55  4791.0 2170.47  4796.9 2169.88  4806.5 2169.89  4833.7 2168.50
  4886.1 2167.40  4922.9 2165.33  4928.8 2165.72  4936.3 2164.29  4959.6 2161.50
  4965.6 2157.88  4971.5 2157.01  4981.1 2152.69  4987.0 2152.20  4988.1 2150.76
  4988.6 2150.26  4994.9 2150.26  4995.4 2150.76  5004.8 2150.92  5032.5 2153.53
  5037.5 2153.41  5045.1 2154.55  5075.3 2157.13  5113.1 2159.41  5193.8 2161.75
  5274.4 2162.78  5347.4 2165.30  5360.0 2165.23  5378.5 2165.93  5397.8 2166.46
#Mann=4,-1,0
  4758.6    0.07       0  4988.1    0.05       0  4995.4    0.07       0
  5378.5   0.035       0
Bank Sta=4988.1,4995.4
Exp/Cntr=0.3,0.1

Type RM Length L Ch R = 1,5529,450,450,450
BEGIN DESCRIPTION:
Stream0137 12.0
END DESCRIPTION:
XS GIS Cut Line= 3
      1796376.38     13912705.14      1796425.00     13912225.00
      1796425.00     13911825.00
#Sta/Elev= 30
  4517.4 2171.72  4547.7 2171.60  4558.1 2170.71  4618.1 2169.02  4647.9 2169.18
  4652.9 2168.50  4698.5 2168.17  4708.5 2167.06  4738.7 2165.83  4778.9 2165.07
  4819.1 2163.21  4852.7 2162.80  4889.4 2160.21  4929.6 2158.71  4947.5 2155.68
  4952.6 2156.41  4959.8 2154.35  4979.9 2151.43  4989.9 2151.36  4993.6 2149.89
  4994.1 2149.39  5000.9 2149.39  5001.4 2149.89  5030.0 2151.30  5080.0 2155.09
  5150.0 2156.27  5270.0 2161.56  5350.0 2166.64  5380.0 2169.53  5400.0 2170.64
#Mann=3,-1,0
  4517.4    0.07       0  4993.6    0.05       0  5001.4    0.07       0
Bank Sta=4993.6,5001.4
Exp/Cntr=0.3,0.1

Type RM Length L Ch R = 1,5079,469,469,469
BEGIN DESCRIPTION:
Stream0137 11.0
END DESCRIPTION:
XS GIS Cut Line= 3
      1796624.99     13912475.01      1796825.00     13912175.00
      1796925.01     13911974.98
#Sta/Elev= 30
  4635.2 2162.68  4648.7 2162.03  4678.8 2161.90  4684.8 2161.15  4735.9 2158.75
  4750.9 2157.68  4802.0 2155.75  4874.1 2153.85  4916.1 2153.19  4937.2 2151.36
  4952.2 2150.70  4973.2 2148.53  4998.6 2147.83  5005.8 2146.81  5006.3 2146.31
  5013.2 2146.31  5013.7 2146.81  5018.1 2147.34  5032.1 2147.79  5040.5 2149.83
  5048.9 2152.74  5054.5 2153.68  5071.2 2155.91  5085.2 2156.61  5107.6 2159.79
  5121.6 2161.11  5143.9 2164.29  5152.3 2165.07  5166.3 2167.39  5219.4 2171.15
#Mann=3,-1,0
  4635.2    0.07       0  5005.8    0.05       0  5013.7    0.07       0
Bank Sta=5005.8,5013.7
Exp/Cntr=0.3,0.1

Type RM Length L Ch R = 1,4610,442,442,442
BEGIN DESCRIPTION:
Stream0137 10.0
END DESCRIPTION:
XS GIS Cut Line= 3
      1796924.99     13912525.00      1797225.00     13912375.00
      1797324.97     13912275.03
#Sta/Elev= 30
  4664.8 2158.33  4687.2 2157.84  4695.6 2156.93  4701.1 2156.94  4754.2 2153.57
  4776.6 2152.95  4790.6 2152.11  4812.9 2151.68  4866.1 2148.37  4896.8 2149.53
  4910.8 2149.11  4924.7 2148.12  4941.5 2148.00  4963.9 2146.47  4969.5 2145.38
  4986.2 2143.40  4991.8 2141.81  4993.5 2140.87  4994.0 2140.37  5000.9 2140.37
  5001.4 2140.87  5014.4 2141.52  5028.5 2143.45  5042.6 2149.05  5070.9 2155.20
  5099.2 2159.06  5106.3 2159.58  5113.4 2161.95  5138.1 2166.14  5141.6 2166.14
#Mann=3,-1,0
  4664.8    0.07       0  4993.5    0.05       0  5001.4    0.07       0
Bank Sta=4993.5,5001.4
Exp/Cntr=0.3,0.1

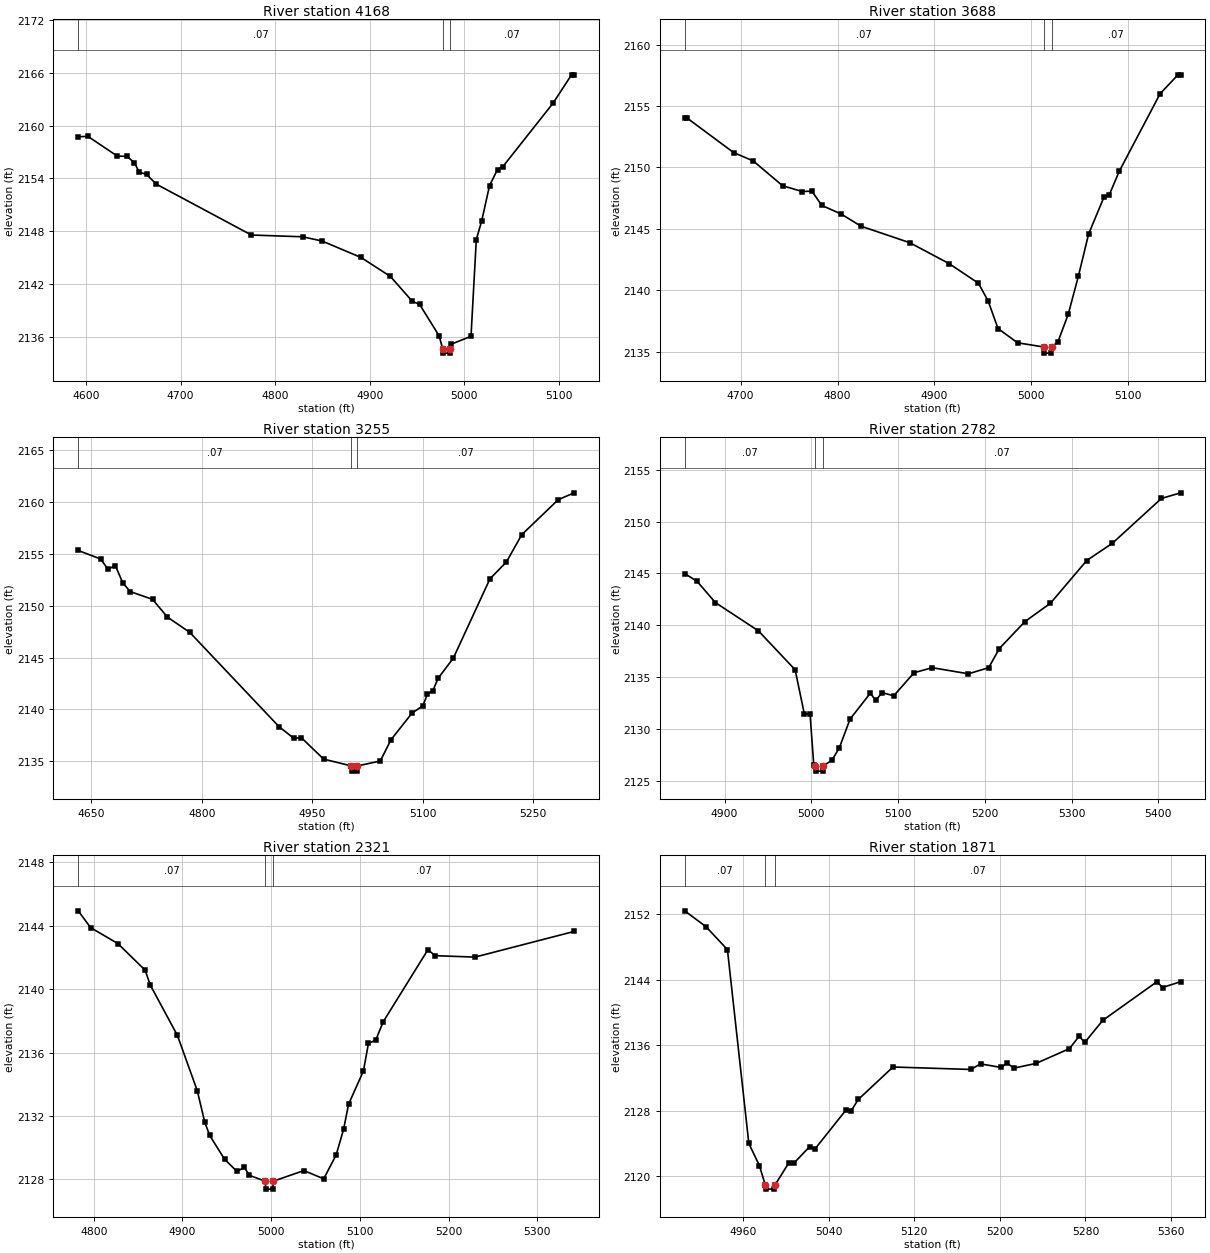
Type RM Length L Ch R = 1,4168,480,480,480
BEGIN DESCRIPTION:
Stream0137 9.0
END DESCRIPTION:
XS GIS Cut Line= 3
      1797124.98     13912775.00      1797525.00     13912675.00
      1797624.97     13912625.01
#Sta/Elev= 30
  4591.9 2158.73  4602.2 2158.77  4633.1 2156.54  4643.5 2156.50  4651.2 2155.78
  4656.3 2154.73  4664.1 2154.45  4674.4 2153.35  4774.9 2147.57  4829.0 2147.37
  4849.6 2146.89  4890.8 2145.02  4921.8 2142.87  4945.0 2140.04  4952.7 2139.69
  4973.3 2136.12  4977.0 2134.66  4977.5 2134.16  4984.5 2134.16  4985.0 2134.66
  4986.2 2135.18  5007.0 2136.07  5012.6 2147.06  5018.2 2149.13  5026.6 2153.19
  5035.0 2155.01  5040.6 2155.33  5093.7 2162.54  5113.2 2165.76  5116.0 2165.76
#Mann=3,-1,0
  4591.9    0.07       0  4977.0    0.05       0  4985.0    0.07       0
Bank Sta=4977,4985
Exp/Cntr=0.3,0.1

Type RM Length L Ch R = 1,3688,433,433,433
BEGIN DESCRIPTION:
Stream0137 8.0
END DESCRIPTION:
XS GIS Cut Line= 3
      1797274.99     13913175.00      1797625.00     13913125.00
      1797775.02     13913074.99
#Sta/Elev= 30
  4642.3 2154.02  4644.8 2154.02  4692.8 2151.21  4713.0 2150.53  4743.3 2148.51
  4763.5 2148.04  4773.6 2148.07  4783.7 2146.91  4803.9 2146.20  4824.1 2145.22
  4874.6 2143.87  4915.1 2142.17  4945.4 2140.57  4955.5 2139.11  4965.6 2136.88
  4985.8 2135.72  5012.9 2135.38  5013.4 2134.88  5020.5 2134.88  5021.0 2135.38
  5027.5 2135.82  5038.0 2138.03  5048.6 2141.17  5059.1 2144.59  5074.9 2147.58
  5080.2 2147.73  5090.7 2149.69  5132.9 2156.01  5151.3 2157.54  5154.0 2157.54
#Mann=3,-1,0
  4642.3    0.07       0  5012.9    0.05       0  5021.0    0.07       0
Bank Sta=5012.9,5021
Exp/Cntr=0.3,0.1

Type RM Length L Ch R = 1,3255,473,473,473
BEGIN DESCRIPTION:
Stream0137 7.0
END DESCRIPTION:
XS GIS Cut Line= 3
      1797324.98     13913575.00      1797675.00     13913525.00
      1797924.98     13913325.02
#Sta/Elev= 30
  4632.2 2155.34  4662.5 2154.52  4672.6 2153.54  4682.7 2153.87  4692.8 2152.21
  4702.9 2151.37  4733.2 2150.62  4753.4 2148.91  4783.7 2147.44  4905.0 2138.34
  4925.2 2137.21  4935.3 2137.28  4965.6 2135.21  5003.3 2134.55  5003.8 2134.05
  5010.9 2134.05  5011.4 2134.55  5042.6 2135.03  5057.0 2137.07  5085.8 2139.66
  5100.2 2140.34  5106.6 2141.48  5113.8 2141.79  5121.0 2142.99  5141.9 2144.97
  5191.5 2152.60  5213.9 2154.23  5234.7 2156.86  5284.3 2160.24  5305.9 2160.90
#Mann=3,-1,0
  4632.2    0.07       0  5003.3    0.05       0  5011.4    0.07       0
Bank Sta=5003.3,5011.4
Exp/Cntr=0.3,0.1

Type RM Length L Ch R = 1,2782,461,461,461
BEGIN DESCRIPTION:
Stream0137 6.0
END DESCRIPTION:
XS GIS Cut Line= 3
      1797674.98     13914025.02      1797775.00     13913925.00
      1798025.02     13913574.98
#Sta/Elev= 30
  4854.1 2144.98  4868.3 2144.24  4889.5 2142.18  4939.0 2139.46  4981.4 2135.70
  4992.0 2131.44  4998.6 2131.44  5002.9 2126.47  5004.6 2126.42  5005.1 2125.92
  5013.0 2125.92  5013.5 2126.42  5023.8 2126.96  5032.4 2128.18  5044.7 2130.94
  5068.1 2133.44  5074.2 2132.74  5081.6 2133.49  5095.1 2133.19  5118.4 2135.41
  5139.3 2135.90  5181.1 2135.31  5204.5 2135.90  5216.8 2137.75  5246.3 2140.35
  5275.7 2142.12  5317.5 2146.24  5347.0 2147.90  5403.6 2152.23  5425.7 2152.77
#Mann=3,-1,0
  4854.1    0.07       0  5004.6    0.05       0  5013.5    0.07       0
Bank Sta=5004.6,5013.5
Exp/Cntr=0.3,0.1

Type RM Length L Ch R = 1,2321,450,450,450
BEGIN DESCRIPTION:
Stream0137 5.0
END DESCRIPTION:
XS GIS Cut Line= 3
      1797874.97     13914325.01      1798075.00     13914225.00
      1798224.98     13913925.04
#Sta/Elev= 30
  4782.5 2144.94  4796.5 2143.88  4827.3 2142.87  4858.0 2141.19  4863.6 2140.27
  4894.3 2137.08  4916.7 2133.59  4925.1 2131.61  4930.7 2130.77  4947.4 2129.27
  4961.4 2128.50  4969.8 2128.75  4975.4 2128.25  4993.3 2127.88  4993.8 2127.38
  5001.8 2127.38  5002.3 2127.88  5036.9 2128.55  5059.2 2128.03  5073.2 2129.53
  5081.6 2131.15  5087.2 2132.73  5104.0 2134.84  5109.6 2136.57  5117.9 2136.79
  5126.3 2137.94  5176.6 2142.48  5185.0 2142.11  5229.7 2142.02  5341.5 2143.64
#Mann=3,-1,0
  4782.5    0.07       0  4993.3    0.05       0  5002.3    0.07       0
Bank Sta=4993.3,5002.3
Exp/Cntr=0.3,0.1

Type RM Length L Ch R = 1,1871,446,446,446
BEGIN DESCRIPTION:
Stream0137 4.0
END DESCRIPTION:
XS GIS Cut Line= 3
      1798375.00     13914624.98      1798375.00     13914525.00
      1798475.00     13914174.99
#Sta/Elev= 30
  4905.1 2152.38  4925.1 2150.44  4945.1 2147.65  4965.1 2124.03  4975.1 2121.29
  4980.5 2118.95  4981.0 2118.45  4989.1 2118.45  4989.6 2118.95  5002.6 2121.67
  5007.7 2121.67  5022.0 2123.63  5027.2 2123.38  5055.8 2128.06  5061.0 2128.03
  5067.5 2129.38  5100.0 2133.34  5172.8 2133.04  5181.9 2133.72  5201.4 2133.28
  5206.6 2133.84  5213.1 2133.20  5233.9 2133.78  5265.1 2135.58  5274.2 2137.10
  5279.4 2136.33  5296.3 2139.03  5347.0 2143.74  5352.2 2143.03  5369.1 2143.74
#Mann=3,-1,0
  4905.1    0.07       0  4980.5    0.05       0  4989.6    0.07       0
Bank Sta=4980.5,4989.6
Exp/Cntr=0.3,0.1

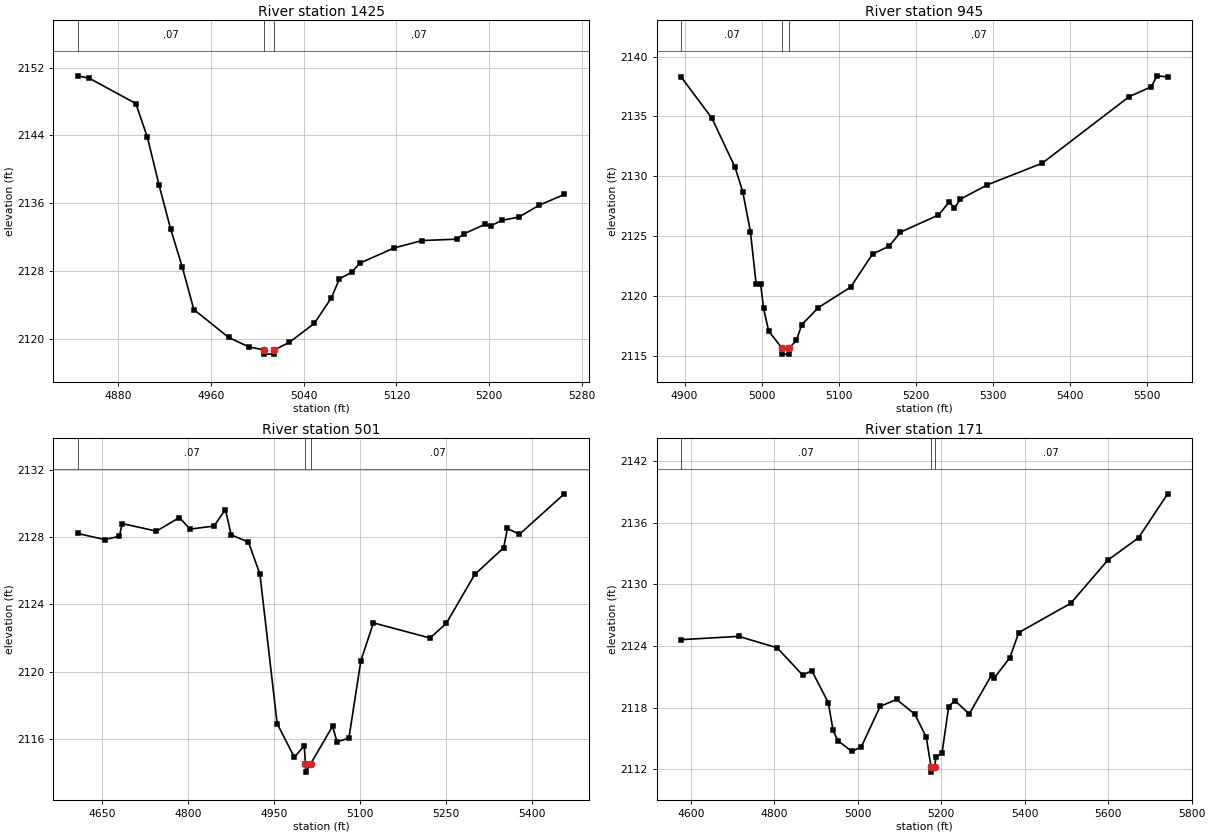
Type RM Length L Ch R = 1,1425,480,480,480
BEGIN DESCRIPTION:
Stream0137 3.0
END DESCRIPTION:
XS GIS Cut Line= 3
      1798775.00     13914624.96      1798775.00     13914475.00
      1798675.01     13914225.02
#Sta/Elev= 30
  4845.5 2151.04  4855.5 2150.75  4895.5 2147.77  4905.5 2143.78  4915.5 2138.16
  4925.5 2132.96  4935.5 2128.47  4945.5 2123.43  4975.5 2120.13  4993.0 2119.01
  5005.7 2118.66  5006.2 2118.16  5014.3 2118.16  5014.8 2118.66  5027.8 2119.55
  5049.3 2121.79  5064.1 2124.83  5070.9 2127.05  5081.6 2127.84  5088.4 2128.90
  5118.0 2130.70  5142.2 2131.58  5171.8 2131.74  5178.6 2132.40  5196.1 2133.48
  5201.4 2133.32  5210.9 2133.96  5225.7 2134.36  5243.2 2135.77  5264.7 2137.02
#Mann=3,-1,0
  4845.5    0.07       0  5005.7    0.05       0  5014.8    0.07       0
Bank Sta=5005.7,5014.8
Exp/Cntr=0.3,0.1

Type RM Length L Ch R = 1,945,444,444,444
BEGIN DESCRIPTION:
Stream0137 2.0
END DESCRIPTION:
XS GIS Cut Line= 3
      1799225.00     13914474.97      1799225.00     13914375.00
      1798824.98     13914024.98
#Sta/Elev= 30
  4895.5 2138.31  4935.5 2134.86  4965.5 2130.76  4975.5 2128.72  4985.5 2125.36
  4993.0 2120.95  4998.8 2120.95  5002.6 2118.94  5009.2 2117.05  5026.5 2115.62
  5027.0 2115.12  5035.2 2115.12  5035.7 2115.62  5045.3 2116.27  5051.9 2117.57
  5073.8 2119.02  5115.5 2120.72  5144.0 2123.49  5165.8 2124.16  5180.1 2125.32
  5229.4 2126.75  5243.7 2127.85  5250.3 2127.33  5257.9 2128.08  5293.0 2129.28
  5364.2 2131.09  5477.1 2136.66  5505.6 2137.48  5513.2 2138.40  5527.0 2138.31
#Mann=3,-1,0
  4895.5    0.07       0  5026.5    0.05       0  5035.7    0.07       0
Bank Sta=5026.5,5035.7
Exp/Cntr=0.3,0.1

Type RM Length L Ch R = 1,501,330,330,330
BEGIN DESCRIPTION:
Stream0137 1.0
END DESCRIPTION:
XS GIS Cut Line= 3
      1799605.80     13914511.83      1799575.00     13914125.00
      1799225.03     13913825.02
#Sta/Elev= 30
  4606.9 2128.22  4653.9 2127.86  4679.5 2128.05  4684.5 2128.81  4744.2 2128.36
  4784.3 2129.17  4802.7 2128.48  4844.5 2128.66  4864.5 2129.64  4874.6 2128.14
  4904.7 2127.71  4924.7 2125.81  4954.8 2116.91  4984.9 2114.90  5002.1 2115.60
  5004.1 2114.52  5004.6 2114.02  5013.3 2114.52  5051.5 2116.75  5059.2 2115.82
  5080.0 2116.04  5100.9 2120.66  5122.8 2122.90  5221.6 2122.00  5250.1 2122.88
  5299.5 2125.78  5350.0 2127.37  5356.6 2128.52  5377.5 2128.17  5455.9 2130.58
#Mann=3,-1,0
  4606.9    0.07       0  5004.1    0.05       0  5013.3    0.07       0
Bank Sta=5004.1,5013.3
Exp/Cntr=0.3,0.1

Type RM Length L Ch R = 1,171,0,0,0
BEGIN DESCRIPTION:
Stream0137 0.0
END DESCRIPTION:
XS GIS Cut Line= 4
      1799771.58     13914375.32      1799874.02     13914090.59
      1799785.48     13913906.56      1799209.57     13913585.65
#Sta/Elev= 30
  4576.4 2124.62  4714.5 2124.94  4806.6 2123.83  4868.1 2121.16  4889.5 2121.61
  4929.2 2118.49  4940.7 2115.81  4951.8 2114.80  4985.6 2113.75  5008.2 2114.18
  5053.5 2118.13  5093.1 2118.80  5136.5 2117.37  5164.0 2115.14  5175.4 2112.23
  5175.9 2111.73  5184.6 2112.23  5186.8 2113.17  5201.7 2113.57  5217.7 2118.10
  5232.6 2118.69  5266.9 2117.39  5320.6 2121.19  5326.3 2120.87  5364.0 2122.84
  5385.7 2125.31  5510.3 2128.16  5598.9 2132.35  5672.6 2134.53  5742.5 2138.81
#Mann=3,-1,0
  4576.4    0.07       0  5175.4    0.05       0  5184.6    0.07       0
Bank Sta=5175.4,5184.6
Exp/Cntr=0.3,0.1

Chan Stop Cuts=-1