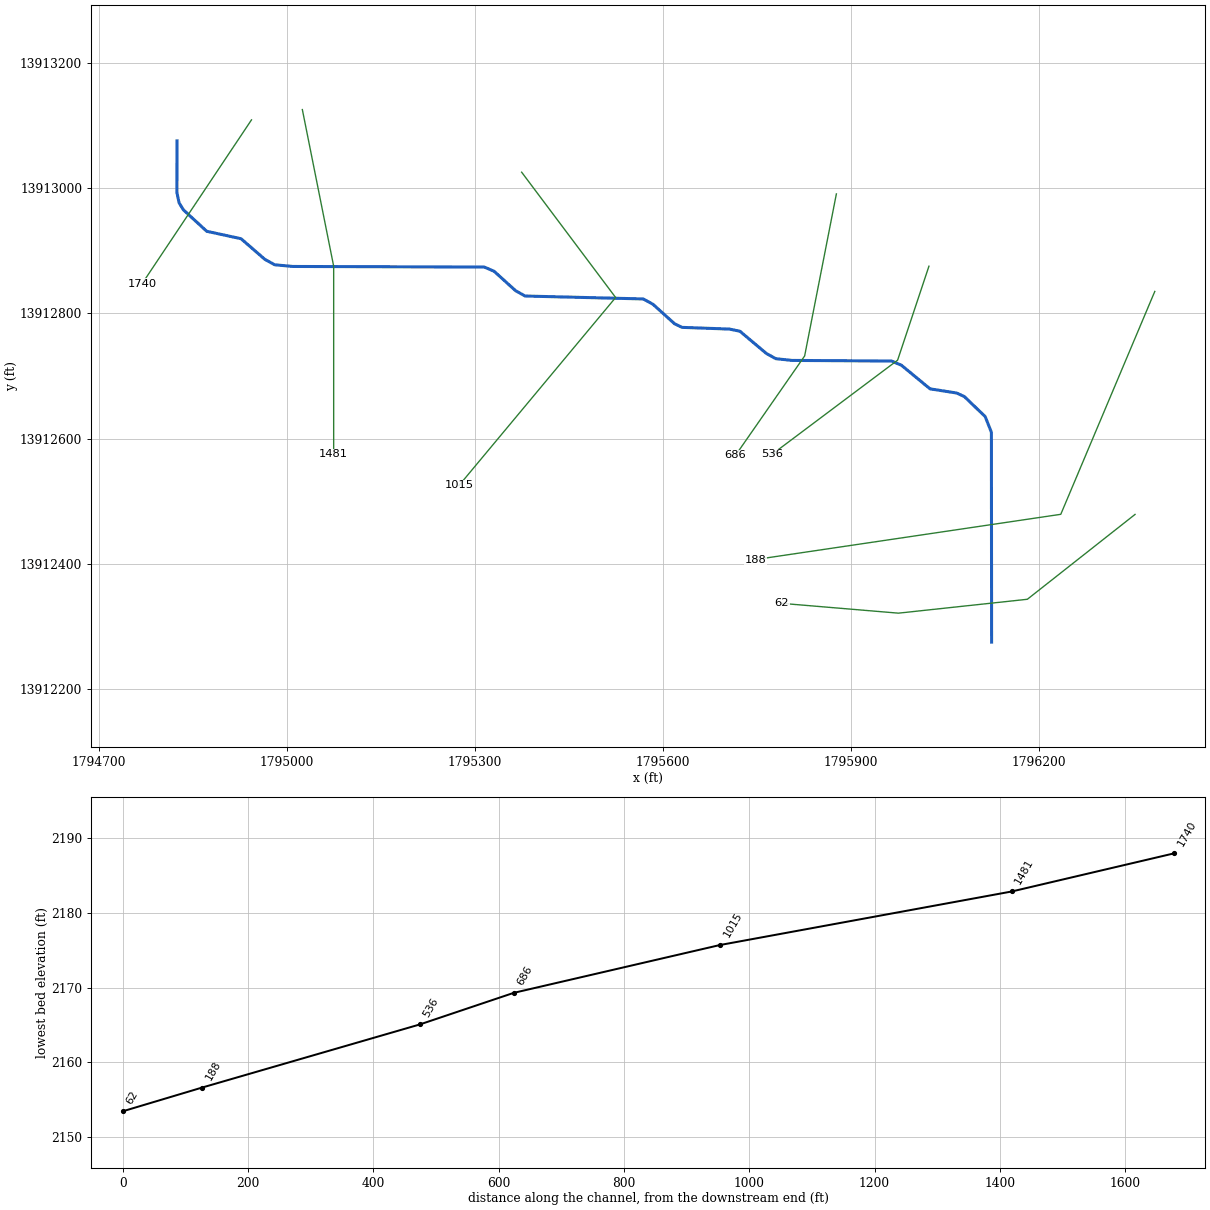
--- Stream0138.prj (project) ---

Proj Title=Stream0138 Base Level Engineering
Current Plan=p01
Default Exp/Contr=0.3,0.1
English Units
Geom File=g01
Flow File=f01
Plan File=p01
BEGIN DESCRIPTION:
Stream0138
END DESCRIPTION:

--- Stream0138.p01 (plan) ---

Plan Title=Multiple Run
Short Identifier=Multiple
Geom File=g01
Flow File=f01
Subcritical Flow
K Sum by GR= 0
Std Step Tol= 0.01
Critical Tol= 0.01
Num of Std Step Trials= 20
Max Error Tol= 0.3
Flow Tol Ratio= 0.001
Split Flow NTrial= 30
Split Flow Tol= 0.02
Split Flow Ratio= 0.02
Log Output Level= 0
Friction Slope Method= 1
Unsteady Friction Slope Method= 2
Unsteady Bridges Friction Slope Method= 1
Parabolic Critical Depth
Global Vel Dist=  1 , 1 , 1
Global Log Level= 0
CheckData=True
Encroach Param= -1, 0, 0, 0
BEGIN DESCRIPTION:
Multiple Run
END DESCRIPTION:

--- Stream0138.f01 (steady flow) ---

Flow Title=Multiple
Number of Profiles=7
Profile Names=10-year,25-year,50-year,1pct_min,100-year,1pct_plu,500-year
River Rch & RM= Stream0138,Reach-1,1740
     358     572     763     495     987    1970    1628
Boundary for River Rch & Prof#=Stream0138,Reach-1,1
Up Type=0
Dn Type=3
Dn Slope=0.005
Boundary for River Rch & Prof#=Stream0138,Reach-1,2
Up Type=0
Dn Type=3
Dn Slope=0.005
Boundary for River Rch & Prof#=Stream0138,Reach-1,3
Up Type=0
Dn Type=3
Dn Slope=0.005
Boundary for River Rch & Prof#=Stream0138,Reach-1,4
Up Type=0
Dn Type=3
Dn Slope=0.005
Boundary for River Rch & Prof#=Stream0138,Reach-1,5
Up Type=0
Dn Type=3
Dn Slope=0.005
Boundary for River Rch & Prof#=Stream0138,Reach-1,6
Up Type=0
Dn Type=3
Dn Slope=0.005
Boundary for River Rch & Prof#=Stream0138,Reach-1,7
Up Type=0
Dn Type=3
Dn Slope=0.005

--- Stream0138.g01 (geometry) ---

Geom Title=Existing Conditions

River Reach=Stream0138,Reach-1
Reach XY= 30
      1794825.00     13913075.00      1794824.75     13912992.96
      1794828.28     13912976.15      1794835.28     13912964.82
      1794872.42     13912930.70      1794927.15     13912918.85
      1794965.33     13912885.79      1794980.93     13912877.24
      1795009.82     13912874.56      1795315.34     13912873.62
      1795331.06     13912866.86      1795365.35     13912835.85
      1795380.53     13912827.38      1795569.06     13912822.74
      1795584.65     13912814.15      1795618.97     13912783.19
      1795630.98     13912777.36      1795706.67     13912774.63
      1795723.40     13912771.14      1795765.35     13912735.85
      1795780.53     13912727.38      1795806.66     13912724.61
      1795965.35     13912723.64      1795981.08     13912716.91
      1796026.78     13912679.23      1796069.17     13912672.59
      1796081.39     13912667.00      1796114.66     13912635.12
      1796124.67     13912609.97      1796125.00     13912275.00

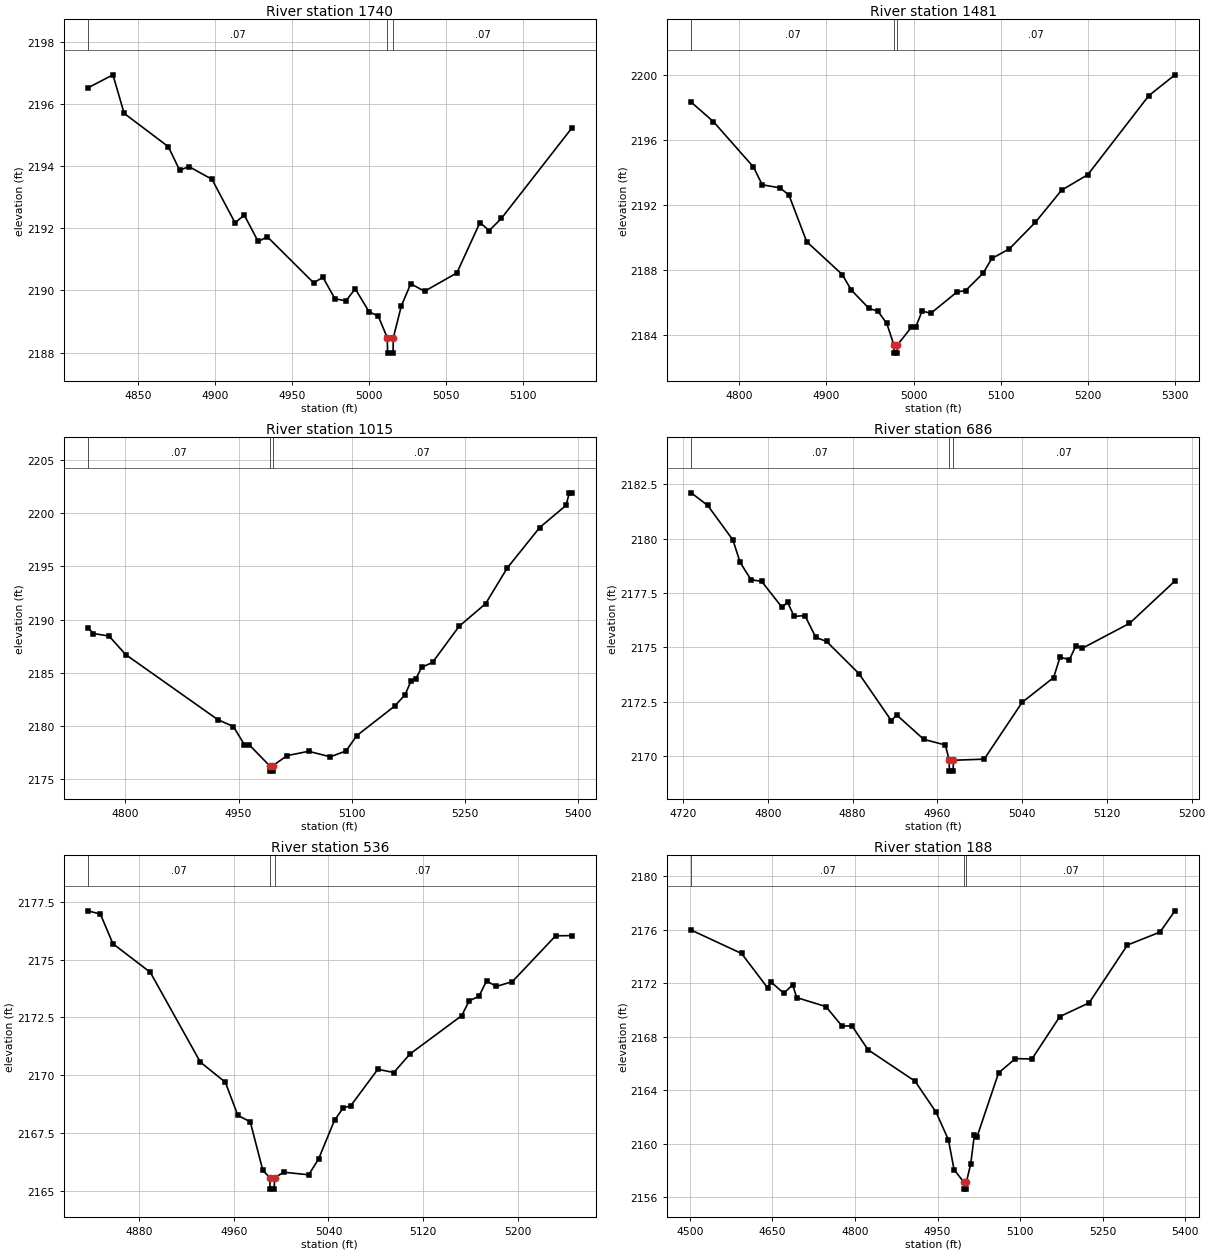
Type RM Length L Ch R = 1,1740,259,259,259
BEGIN DESCRIPTION:
Stream0138 4.0
END DESCRIPTION:
XS GIS Cut Line= 2
      1794943.86     13913108.53      1794769.20     13912846.99
#Sta/Elev= 30
  4817.3 2196.51  4833.6 2196.93  4840.9 2195.69  4869.6 2194.62  4877.0 2193.86
  4883.0 2193.98  4898.0 2193.57  4913.0 2192.17  4919.0 2192.42  4928.0 2191.57
  4934.0 2191.72  4964.1 2190.24  4970.1 2190.42  4977.9 2189.73  4985.1 2189.66
  4991.1 2190.05  5000.1 2189.31  5006.1 2189.17  5011.9 2188.48  5012.2 2187.98
  5015.7 2187.98  5015.9 2188.48  5021.1 2189.50  5027.2 2190.21  5036.2 2189.97
  5057.2 2190.56  5072.2 2192.18  5078.2 2191.92  5086.1 2192.31  5131.8 2195.21
#Mann=3,-1,0
  4817.3    0.07       0  5011.9    0.05       0  5015.9    0.07       0
Bank Sta=5011.9,5015.9
Exp/Cntr=0.3,0.1

Type RM Length L Ch R = 1,1481,466,466,466
BEGIN DESCRIPTION:
Stream0138 3.0
END DESCRIPTION:
XS GIS Cut Line= 3
      1795025.01     13913124.96      1795075.00     13912875.00
      1795075.00     13912575.01
#Sta/Elev= 30
  4745.0 2198.31  4770.5 2197.11  4816.3 2194.33  4826.5 2193.23  4846.9 2193.04
  4857.1 2192.60  4877.5 2189.73  4918.3 2187.71  4928.5 2186.77  4948.9 2185.63
  4959.1 2185.46  4969.3 2184.71  4977.5 2183.38  4977.8 2182.88  4981.3 2182.88
  4981.5 2183.38  4997.4 2184.46  5002.4 2184.46  5009.9 2185.47  5019.9 2185.33
  5049.9 2186.64  5059.9 2186.73  5079.9 2187.80  5089.9 2188.70  5109.9 2189.29
  5139.9 2190.93  5169.9 2192.90  5199.9 2193.85  5269.9 2198.71  5299.9 2199.99
#Mann=3,-1,0
  4745.0    0.07       0  4977.5    0.05       0  4981.5    0.07       0
Bank Sta=4977.5,4981.5
Exp/Cntr=0.3,0.1

Type RM Length L Ch R = 1,1015,329,329,329
BEGIN DESCRIPTION:
Stream0138 2.0
END DESCRIPTION:
XS GIS Cut Line= 3
      1795375.00     13913025.00      1795525.00     13912825.00
      1795275.01     13912525.01
#Sta/Elev= 30
  4750.5 2189.24  4757.8 2188.68  4778.6 2188.44  4800.5 2186.70  4922.4 2180.57
  4943.2 2179.91  4957.8 2178.20  4964.0 2178.20  4991.2 2176.21  4991.5 2175.71
  4995.0 2175.71  4995.2 2176.21  5014.2 2177.17  5042.8 2177.58  5071.4 2177.06
  5092.3 2177.61  5106.6 2179.06  5156.7 2181.84  5170.4 2182.90  5178.2 2184.18
  5184.7 2184.41  5192.5 2185.50  5206.8 2185.95  5242.0 2189.36  5277.1 2191.49
  5305.7 2194.85  5348.7 2198.67  5383.8 2200.77  5387.8 2201.94  5391.0 2201.94
#Mann=3,-1,0
  4750.5    0.07       0  4991.2    0.05       0  4995.2    0.07       0
Bank Sta=4991.2,4995.2
Exp/Cntr=0.3,0.1

Type RM Length L Ch R = 1,686,150,150,150
BEGIN DESCRIPTION:
Stream0138 1.1
END DESCRIPTION:
XS GIS Cut Line= 3
      1795877.26     13912990.31      1795826.62     13912731.73
      1795716.48     13912573.35
#Sta/Elev= 30
  4727.8 2182.10  4743.4 2181.52  4767.2 2179.93  4774.0 2178.90  4784.2 2178.11
  4794.3 2178.03  4813.6 2176.83  4818.7 2177.08  4824.9 2176.42  4835.1 2176.46
  4845.3 2175.46  4855.5 2175.27  4886.1 2173.79  4916.6 2171.63  4921.7 2171.89
  4947.2 2170.77  4967.6 2170.51  4971.2 2169.81  4971.4 2169.31  4974.9 2169.31
  4975.2 2169.81  5004.2 2169.86  5040.0 2172.47  5069.7 2173.61  5075.8 2174.55
  5084.6 2174.43  5090.6 2175.06  5096.9 2174.96  5141.3 2176.10  5184.2 2178.05
#Mann=3,-1,0
  4727.8    0.07       0  4971.2    0.05       0  4975.2    0.07       0
Bank Sta=4971.2,4975.2
Exp/Cntr=0.3,0.1

Type RM Length L Ch R = 1,536,348,348,348
BEGIN DESCRIPTION:
Stream0138 1.0
END DESCRIPTION:
XS GIS Cut Line= 3
      1796025.00     13912875.01      1795975.00     13912725.00
      1795775.02     13912575.02
#Sta/Elev= 30
  4837.0 2177.11  4847.6 2176.97  4858.1 2175.69  4889.7 2174.45  4931.9 2170.57
  4953.0 2169.70  4963.5 2168.27  4974.0 2167.99  4984.6 2165.89  4990.5 2165.58
  4990.7 2165.08  4994.2 2165.08  4994.5 2165.58  5002.4 2165.81  5023.3 2165.70
  5031.6 2166.38  5045.1 2168.06  5052.4 2168.59  5058.7 2168.68  5081.6 2170.26
  5095.1 2170.12  5108.7 2170.92  5152.4 2172.58  5158.7 2173.22  5167.0 2173.42
  5173.3 2174.08  5181.6 2173.84  5195.1 2174.05  5231.6 2176.03  5245.1 2176.04
#Mann=3,-1,0
  4837.0    0.07       0  4990.5    0.05       0  4994.5    0.07       0
Bank Sta=4990.5,4994.5
Exp/Cntr=0.3,0.1

Type RM Length L Ch R = 1,188,126,126,126
BEGIN DESCRIPTION:
Stream0138 0.0
END DESCRIPTION:
XS GIS Cut Line= 3
      1796385.41     13912834.70      1796235.40     13912479.02
      1795748.05     13912406.80
#Sta/Elev= 30
  4502.4 2175.99  4593.9 2174.24  4641.4 2171.66  4646.8 2172.13  4670.5 2171.27
  4686.6 2171.89  4694.2 2170.94  4747.1 2170.27  4776.2 2168.82  4794.5 2168.82
  4823.7 2167.04  4909.0 2164.69  4947.2 2162.37  4969.7 2160.30  4979.8 2158.08
  4998.0 2157.12  4998.3 2156.62  5001.8 2156.62  5002.0 2157.12  5010.1 2158.50
  5016.7 2160.67  5021.7 2160.55  5060.7 2165.31  5091.2 2166.38  5121.3 2166.35
  5171.9 2169.52  5225.2 2170.55  5294.7 2174.87  5353.9 2175.84  5381.1 2177.43
#Mann=3,-1,0
  4502.4    0.07       0  4998.0    0.05       0  5002.0    0.07       0
Bank Sta=4998,5002
Exp/Cntr=0.3,0.1

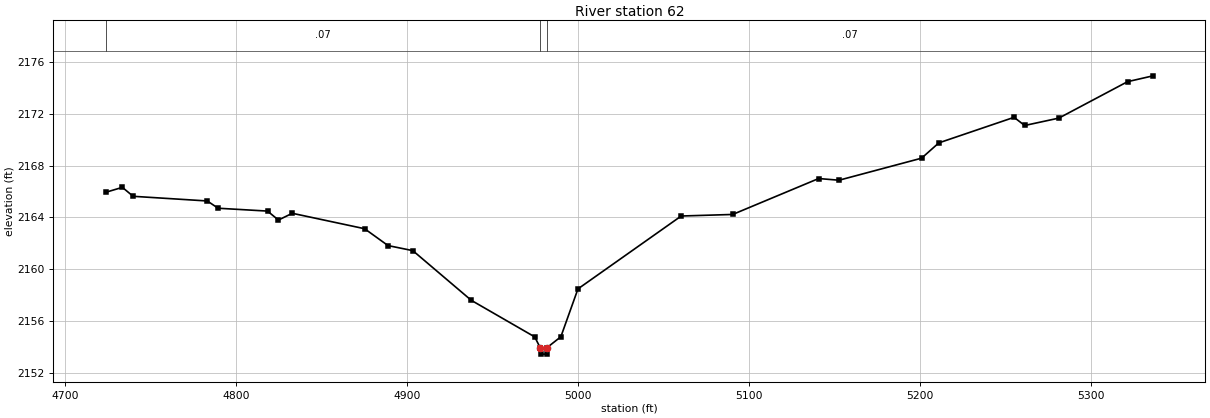
Type RM Length L Ch R = 1,62,0,0,0
BEGIN DESCRIPTION:
Stream0138 0.1
END DESCRIPTION:
XS GIS Cut Line= 4
      1796353.93     13912478.85      1796182.03     13912343.41
      1795976.30     13912321.27      1795790.12     13912336.90
#Sta/Elev= 30
  4723.8 2165.94  4733.5 2166.32  4739.8 2165.63  4783.2 2165.27  4789.5 2164.71
  4818.4 2164.49  4824.8 2163.80  4832.9 2164.32  4875.2 2163.13  4888.9 2161.83
  4903.4 2161.44  4937.6 2157.61  4974.7 2154.79  4977.9 2153.96  4978.1 2153.46
  4981.6 2153.46  4981.9 2153.96  4990.0 2154.80  5000.0 2158.49  5060.4 2164.11
  5090.5 2164.23  5140.8 2167.00  5152.7 2166.87  5201.0 2168.57  5211.1 2169.75
  5255.1 2171.72  5261.3 2171.09  5281.3 2171.66  5321.5 2174.47  5336.4 2174.92
#Mann=3,-1,0
  4723.8    0.07       0  4977.9    0.05       0  4981.9    0.07       0
Bank Sta=4977.9,4981.9
Exp/Cntr=0.3,0.1

Chan Stop Cuts=-1