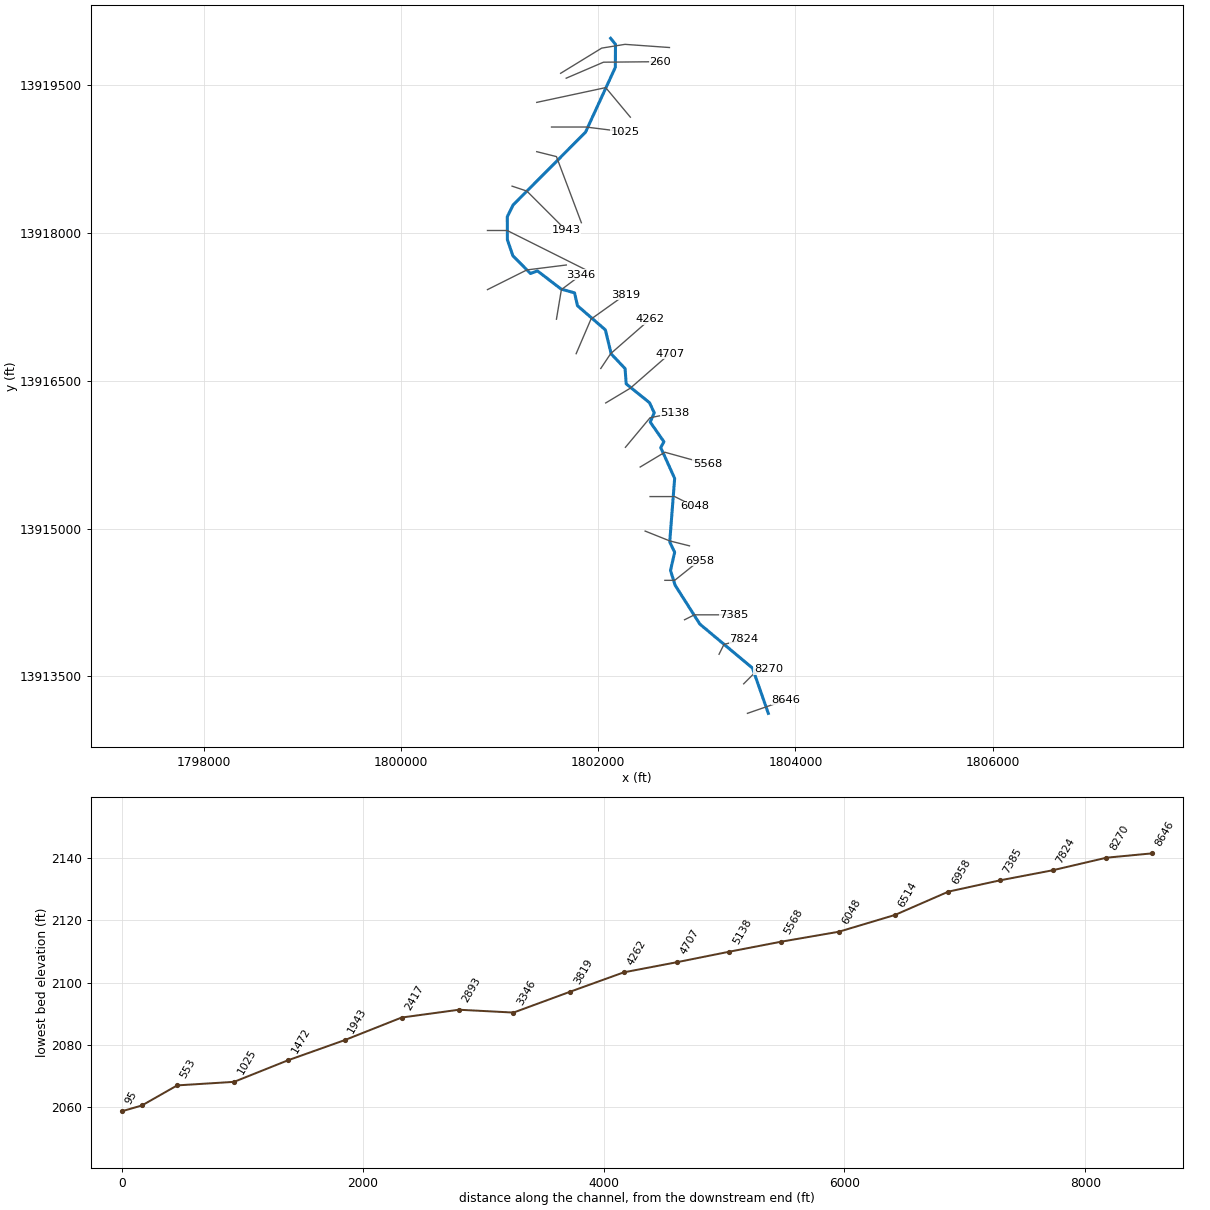
--- Stream0142.prj (project) ---

Proj Title=Stream0142 Base Level Engineering
Current Plan=p01
Default Exp/Contr=0.3,0.1
English Units
Geom File=g01
Flow File=f01
Plan File=p01
BEGIN DESCRIPTION:
Stream0142
END DESCRIPTION:

--- Stream0142.p01 (plan) ---

Plan Title=Multiple Run
Short Identifier=Multiple
Geom File=g01
Flow File=f01
Subcritical Flow
K Sum by GR= 0
Std Step Tol= 0.01
Critical Tol= 0.01
Num of Std Step Trials= 20
Max Error Tol= 0.3
Flow Tol Ratio= 0.001
Split Flow NTrial= 30
Split Flow Tol= 0.02
Split Flow Ratio= 0.02
Log Output Level= 0
Friction Slope Method= 1
Unsteady Friction Slope Method= 2
Unsteady Bridges Friction Slope Method= 1
Parabolic Critical Depth
Global Vel Dist=  1 , 1 , 1
Global Log Level= 0
CheckData=True
Encroach Param= -1, 0, 0, 0
BEGIN DESCRIPTION:
Multiple Run
END DESCRIPTION:

--- Stream0142.f01 (steady flow) ---

Flow Title=Multiple
Number of Profiles=7
Profile Names=10-year,25-year,50-year,1pct_min,100-year,1pct_plu,500-year
River Rch & RM= Stream0142,Reach-1,8646
    1624    2840    4020    2743    5474   10921   10046
River Rch & RM= Stream0142,Reach-1,1025
    1871    3297    4690    3216    6416   12802   11887
Boundary for River Rch & Prof#=Stream0142,Reach-1,1
Up Type=0
Dn Type=3
Dn Slope=0.005
Boundary for River Rch & Prof#=Stream0142,Reach-1,2
Up Type=0
Dn Type=3
Dn Slope=0.005
Boundary for River Rch & Prof#=Stream0142,Reach-1,3
Up Type=0
Dn Type=3
Dn Slope=0.005
Boundary for River Rch & Prof#=Stream0142,Reach-1,4
Up Type=0
Dn Type=3
Dn Slope=0.005
Boundary for River Rch & Prof#=Stream0142,Reach-1,5
Up Type=0
Dn Type=3
Dn Slope=0.005
Boundary for River Rch & Prof#=Stream0142,Reach-1,6
Up Type=0
Dn Type=3
Dn Slope=0.005
Boundary for River Rch & Prof#=Stream0142,Reach-1,7
Up Type=0
Dn Type=3
Dn Slope=0.005

--- Stream0142.g01 (geometry) ---

Geom Title=Existing Conditions

River Reach=Stream0142,Reach-1
Reach XY= 30
      1803725.00     13913125.00      1803564.24     13913584.68
      1803030.62     13914030.62      1802778.62     13914426.50
      1802732.56     13914575.00      1802774.49     13914759.78
      1802724.54     13914864.82      1802774.49     13915509.79
      1802633.28     13915821.78      1802665.42     13915881.55
      1802526.66     13916081.05      1802567.44     13916175.00
      1802519.30     13916277.54      1802282.82     13916468.81
      1802271.52     13916623.73      1802130.70     13916772.62
      1802071.49     13917016.52      1801788.41     13917261.70
      1801758.73     13917392.21      1801622.58     13917430.53
      1801381.55     13917615.41      1801311.66     13917588.65
      1801132.86     13917768.83      1801077.26     13917930.94
      1801076.20     13918164.50      1801135.76     13918284.68
      1801869.77     13919022.45      1802172.74     13919680.94
      1802174.04     13919914.60      1802125.00     13919975.00

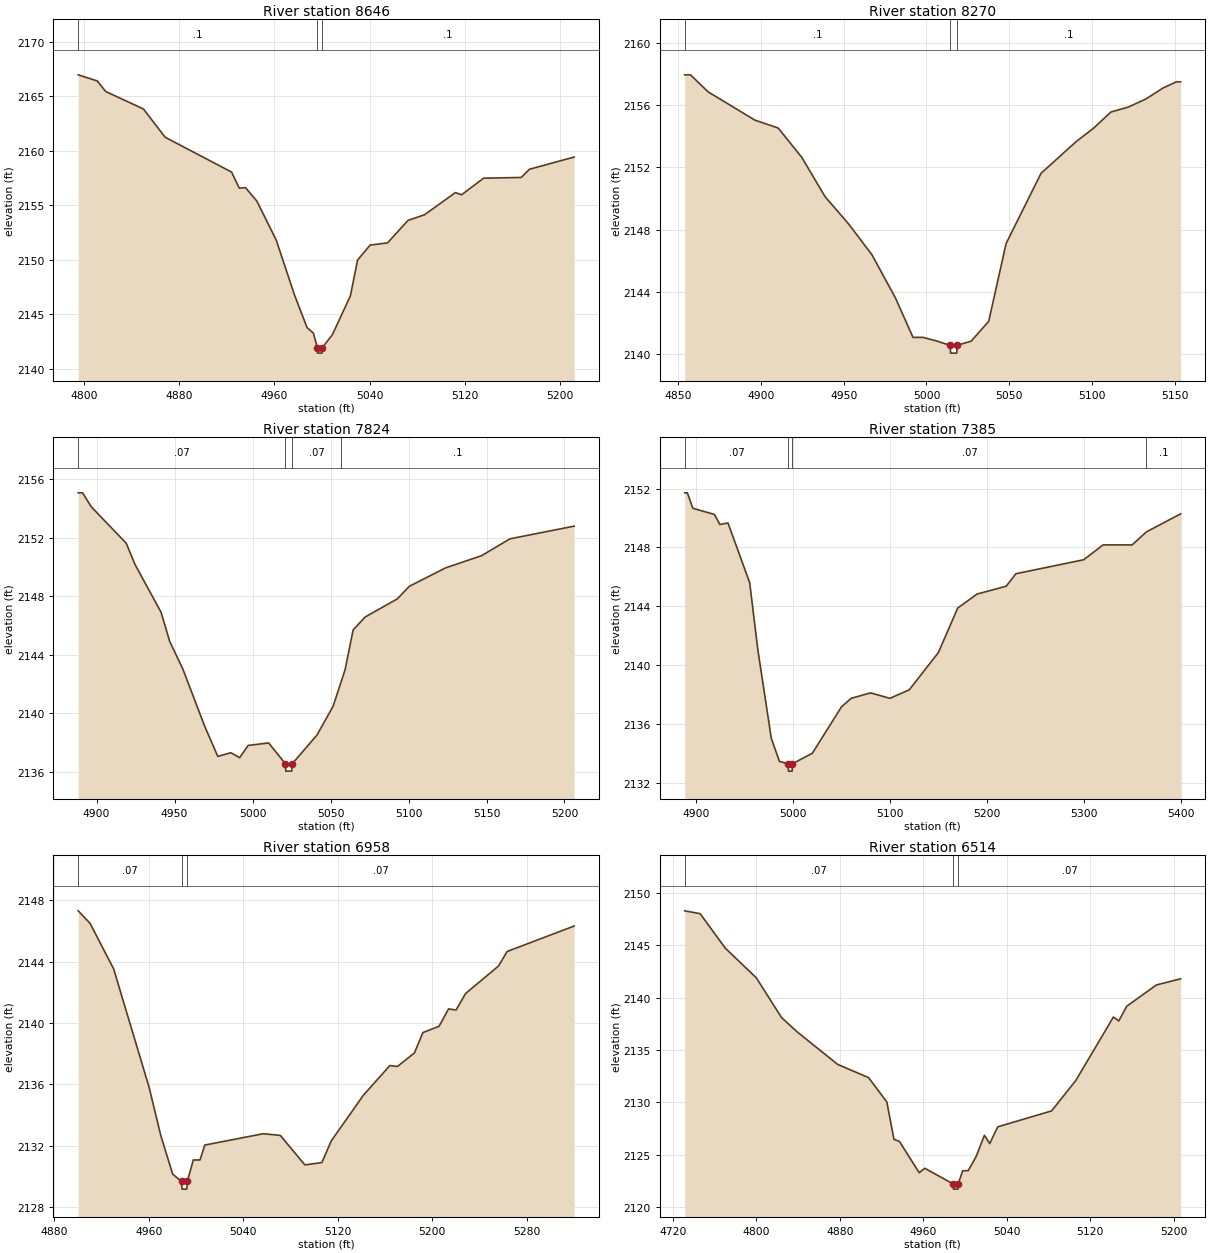
Type RM Length L Ch R = 1,8646,376,376,376
BEGIN DESCRIPTION:
Stream0142 19.0
END DESCRIPTION:
XS GIS Cut Line= 2
      1803513.21     13913125.35      1803906.94     13913261.79
#Sta/Elev= 30
  4795.1 2166.96  4811.1 2166.40  4818.2 2165.43  4849.9 2163.83  4868.1 2161.24
  4924.0 2158.04  4930.4 2156.57  4935.7 2156.61  4945.2 2155.38  4961.5 2151.80
  4976.9 2146.75  4987.4 2143.78  4992.7 2143.28  4996.0 2141.94  4996.2 2141.44
  4999.9 2141.44  5000.2 2141.94  5008.7 2143.14  5023.8 2146.69  5029.8 2149.97
  5040.4 2151.35  5055.0 2151.55  5072.2 2153.61  5086.1 2154.13  5112.0 2156.16
  5117.2 2155.96  5135.7 2157.48  5167.4 2157.55  5174.2 2158.30  5211.8 2159.42
#Mann=3,-1,0
  4795.1     0.1       0  4996.0    0.05       0  5000.2     0.1       0
Bank Sta=4996,5000.2
Exp/Cntr=0.3,0.1

Type RM Length L Ch R = 1,8270,446,446,446
BEGIN DESCRIPTION:
Stream0142 18.0
END DESCRIPTION:
XS GIS Cut Line= 3
      1803475.01     13913425.01      1803575.00     13913525.00
      1803724.98     13913574.99
#Sta/Elev= 30
  4854.0 2157.94  4857.5 2157.94  4868.1 2156.85  4896.4 2155.03  4910.5 2154.52
  4924.7 2152.64  4938.8 2150.11  4953.0 2148.36  4967.1 2146.38  4981.3 2143.60
  4991.9 2141.07  4995.4 2141.07  4998.0 2141.07  5005.9 2140.85  5014.3 2140.56
  5014.6 2140.06  5018.3 2140.06  5018.6 2140.56  5027.0 2140.83  5037.6 2142.10
  5048.1 2147.10  5069.2 2151.61  5090.3 2153.64  5100.8 2154.50  5111.4 2155.55
  5121.9 2155.87  5132.4 2156.38  5143.0 2157.10  5150.9 2157.49  5153.5 2157.49
#Mann=3,-1,0
  4854.0     0.1       0  5014.3    0.05       0  5018.6     0.1       0
Bank Sta=5014.3,5018.6
Exp/Cntr=0.3,0.1

Type RM Length L Ch R = 1,7824,439,439,439
BEGIN DESCRIPTION:
Stream0142 17.0
END DESCRIPTION:
XS GIS Cut Line= 3
      1803224.98     13913724.97      1803275.00     13913825.00
      1803475.01     13913875.00
#Sta/Elev= 30
  4888.2 2155.08  4891.0 2155.08  4896.6 2154.12  4919.0 2151.63  4924.6 2150.18
  4941.3 2146.91  4946.9 2144.90  4955.3 2143.02  4969.3 2139.10  4977.7 2137.04
  4986.1 2137.29  4991.7 2136.95  4997.2 2137.79  5010.3 2137.96  5021.1 2136.53
  5021.3 2136.03  5025.1 2136.03  5025.4 2136.53  5041.3 2138.50  5051.6 2140.46
  5056.4 2142.02  5059.3 2142.96  5064.5 2145.70  5072.2 2146.58  5092.8 2147.82
  5100.5 2148.68  5123.7 2149.94  5146.9 2150.78  5165.0 2151.93  5206.2 2152.80
#Mann=4,-1,0
  4888.2    0.07       0  5021.1    0.05       0  5025.4    0.07       0
  5056.4     0.1       0
Bank Sta=5021.1,5025.4
Exp/Cntr=0.3,0.1

Type RM Length L Ch R = 1,7385,427,427,427
BEGIN DESCRIPTION:
Stream0142 16.0
END DESCRIPTION:
XS GIS Cut Line= 3
      1802875.02     13914075.01      1802975.00     13914125.00
      1803375.01     13914125.00
#Sta/Elev= 30
  4888.0 2151.71  4890.8 2151.71  4896.4 2150.66  4918.7 2150.24  4924.3 2149.56
  4932.7 2149.66  4955.1 2145.60  4963.5 2141.04  4977.4 2135.02  4985.8 2133.45
  4994.8 2133.29  4995.1 2132.79  4998.9 2132.79  4999.2 2133.29  5019.8 2134.01
  5049.8 2137.16  5059.8 2137.74  5079.8 2138.11  5099.8 2137.74  5119.8 2138.32
  5149.8 2140.85  5169.8 2143.88  5189.8 2144.83  5219.8 2145.36  5229.8 2146.21
  5299.8 2147.16  5319.8 2148.17  5349.8 2148.17  5364.4 2149.05  5399.8 2150.28
#Mann=4,-1,0
  4888.0    0.07       0  4994.8    0.05       0  4999.2    0.07       0
  5364.4     0.1       0
Bank Sta=4994.8,4999.2
Exp/Cntr=0.3,0.1

Type RM Length L Ch R = 1,6958,444,444,444
BEGIN DESCRIPTION:
Stream0142 15.0
END DESCRIPTION:
XS GIS Cut Line= 3
      1802675.05     13914475.00      1802775.00     13914475.00
      1803024.99     13914674.99
#Sta/Elev= 30
  4900.1 2147.31  4910.1 2146.50  4930.1 2143.53  4960.1 2135.83  4970.1 2132.66
  4980.1 2130.16  4987.6 2129.68  4988.0 2129.18  4992.1 2129.18  4992.5 2129.68
  4997.6 2131.08  5003.3 2131.08  5007.3 2132.05  5056.9 2132.79  5071.3 2132.68
  5092.1 2130.76  5106.5 2130.91  5114.5 2132.33  5141.7 2135.30  5164.1 2137.23
  5170.5 2137.17  5184.9 2138.05  5192.1 2139.38  5205.8 2139.79  5213.8 2140.92
  5220.2 2140.85  5228.2 2141.92  5256.2 2143.72  5263.4 2144.66  5320.2 2146.32
#Mann=3,-1,0
  4900.1    0.07       0  4987.6    0.05       0  4992.5    0.07       0
Bank Sta=4987.6,4992.5
Exp/Cntr=0.3,0.1

Type RM Length L Ch R = 1,6514,466,466,466
BEGIN DESCRIPTION:
Stream0142 14.0
END DESCRIPTION:
XS GIS Cut Line= 3
      1802475.04     13914974.99      1802725.00     13914875.00
      1802925.02     13914824.99
#Sta/Elev= 30
  4731.2 2148.28  4746.0 2148.01  4770.2 2144.71  4799.8 2141.89  4824.1 2138.08
  4838.9 2136.73  4877.9 2133.61  4907.5 2132.35  4925.0 2130.02  4931.8 2126.46
  4937.1 2126.25  4956.0 2123.27  4961.4 2123.69  4988.5 2122.20  4988.9 2121.70
  4993.1 2121.70  4993.4 2122.20  4997.7 2123.46  5003.0 2123.46  5010.7 2124.84
  5018.5 2126.84  5023.6 2126.05  5031.3 2127.65  5082.9 2129.17  5106.1 2132.07
  5142.2 2138.14  5147.3 2137.76  5155.0 2139.17  5183.4 2141.20  5206.6 2141.79
#Mann=3,-1,0
  4731.2    0.07       0  4988.5    0.05       0  4993.4    0.07       0
Bank Sta=4988.5,4993.4
Exp/Cntr=0.3,0.1

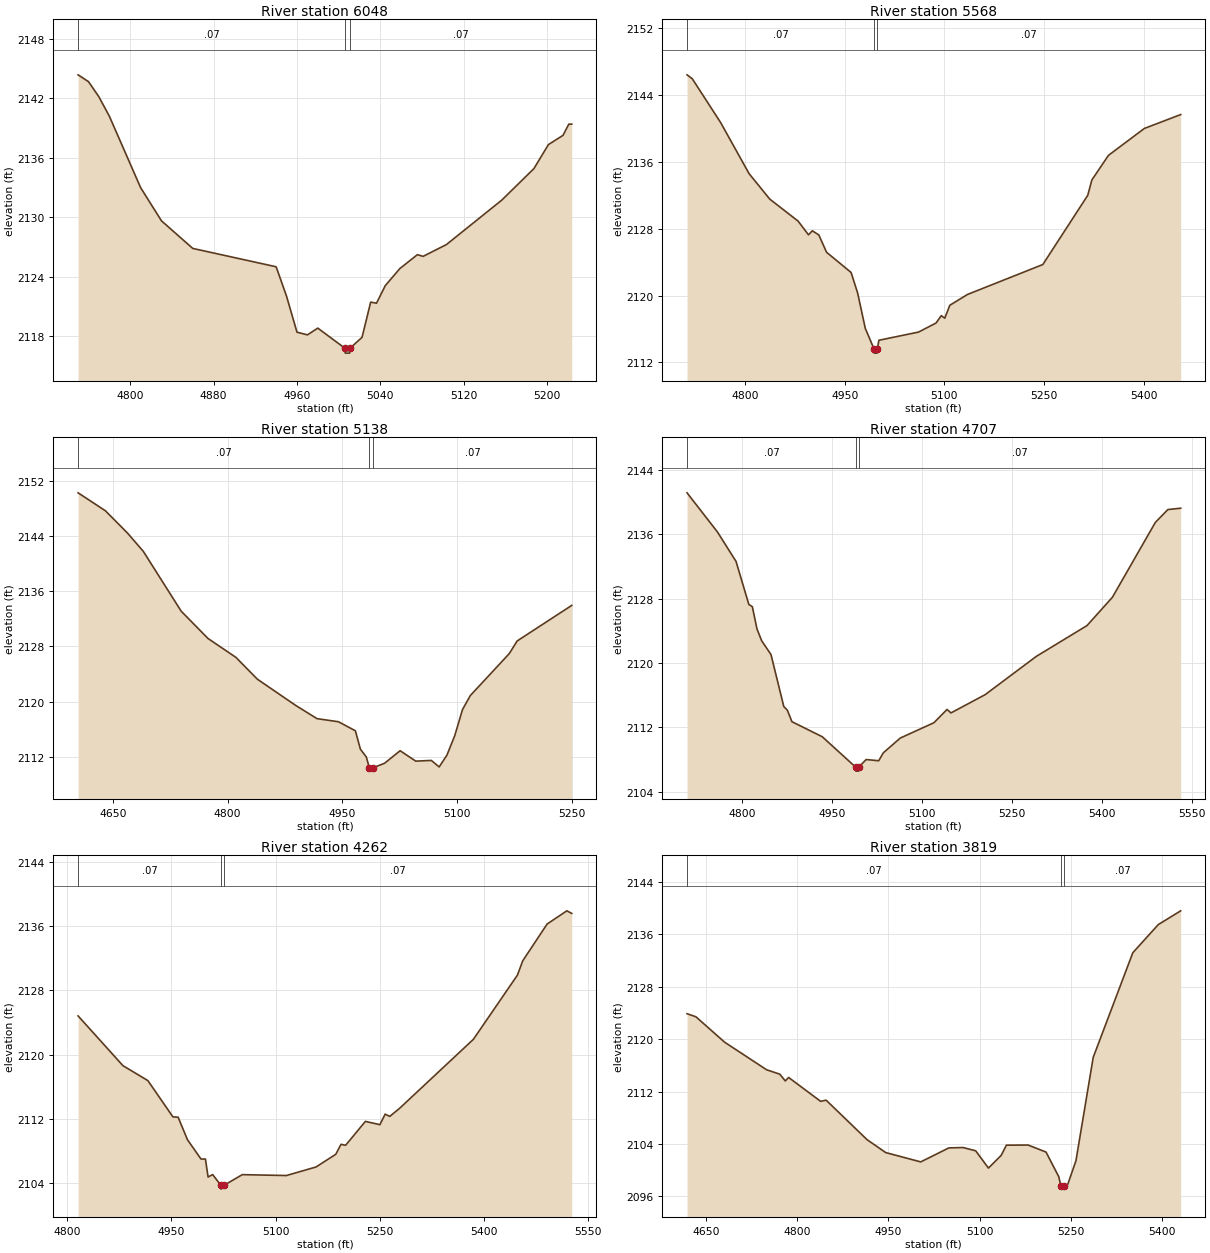
Type RM Length L Ch R = 1,6048,480,480,480
BEGIN DESCRIPTION:
Stream0142 13.0
END DESCRIPTION:
XS GIS Cut Line= 3
      1802525.01     13915325.00      1802775.00     13915325.00
      1802975.00     13915225.00
#Sta/Elev= 30
  4750.0 2144.36  4760.0 2143.67  4770.0 2142.14  4780.0 2140.19  4810.0 2132.99
  4830.0 2129.65  4860.0 2126.87  4940.0 2125.02  4950.0 2122.05  4960.0 2118.43
  4970.0 2118.16  4980.0 2118.84  5005.9 2116.82  5006.3 2116.32  5010.5 2116.32
  5010.9 2116.82  5022.4 2117.91  5030.7 2121.46  5036.3 2121.35  5044.7 2123.12
  5058.7 2124.84  5075.5 2126.24  5081.0 2126.07  5103.4 2127.26  5156.5 2131.74
  5187.3 2134.91  5201.2 2137.33  5215.2 2138.26  5220.8 2139.39  5223.6 2139.39
#Mann=3,-1,0
  4750.0    0.07       0  5005.9    0.05       0  5010.9    0.07       0
Bank Sta=5005.9,5010.9
Exp/Cntr=0.3,0.1

Type RM Length L Ch R = 1,5568,430,430,430
BEGIN DESCRIPTION:
Stream0142 12.0
END DESCRIPTION:
XS GIS Cut Line= 3
      1802425.01     13915625.01      1802675.00     13915775.00
      1803109.70     13915654.61
#Sta/Elev= 30
  4712.9 2146.45  4720.7 2145.99  4763.4 2140.74  4806.2 2134.62  4837.3 2131.57
  4880.0 2128.93  4895.6 2127.29  4901.4 2127.77  4911.1 2127.28  4922.8 2125.20
  4959.7 2122.78  4969.5 2120.33  4981.1 2116.07  4994.2 2113.62  4994.5 2113.12
  4998.8 2113.12  4999.2 2113.62  5001.5 2114.66  5061.1 2115.64  5087.4 2116.72
  5095.4 2117.61  5100.6 2117.30  5108.2 2118.85  5134.9 2120.15  5248.1 2123.73
  5315.7 2132.02  5321.9 2133.86  5346.9 2136.81  5400.9 2140.03  5455.5 2141.69
#Mann=3,-1,0
  4712.9    0.07       0  4994.2    0.05       0  4999.2    0.07       0
Bank Sta=4994.2,4999.2
Exp/Cntr=0.3,0.1

Type RM Length L Ch R = 1,5138,431,431,431
BEGIN DESCRIPTION:
Stream0142 11.0
END DESCRIPTION:
XS GIS Cut Line= 3
      1802274.98     13915824.97      1802525.00     13916125.00
      1802775.00     13916175.00
#Sta/Elev= 30
  4604.4 2150.27  4640.2 2147.66  4668.9 2144.45  4689.7 2141.78  4739.2 2133.11
  4774.3 2129.15  4810.8 2126.41  4838.7 2123.26  4888.9 2119.45  4916.8 2117.53
  4944.8 2117.08  4967.0 2115.77  4973.5 2113.11  4981.3 2111.97  4985.2 2110.42
  4985.6 2109.92  4990.0 2109.92  4990.4 2110.42  5005.1 2111.06  5025.5 2112.88
  5045.9 2111.37  5066.3 2111.47  5076.5 2110.53  5086.7 2112.24  5096.9 2115.06
  5107.1 2118.86  5117.3 2120.88  5168.3 2126.97  5178.5 2128.79  5249.9 2133.95
#Mann=3,-1,0
  4604.4    0.07       0  4985.2    0.05       0  4990.4    0.07       0
Bank Sta=4985.2,4990.4
Exp/Cntr=0.3,0.1

Type RM Length L Ch R = 1,4707,445,445,445
BEGIN DESCRIPTION:
Stream0142 10.0
END DESCRIPTION:
XS GIS Cut Line= 3
      1802074.98     13916274.99      1802325.00     13916425.00
      1802725.02     13916775.02
#Sta/Elev= 30
  4708.7 2141.15  4759.3 2136.30  4790.4 2132.63  4811.7 2127.30  4817.6 2127.00
  4825.3 2124.25  4833.1 2122.78  4848.7 2121.06  4870.0 2114.61  4875.9 2114.16
  4883.6 2112.72  4934.2 2110.85  4989.8 2107.08  4990.3 2106.58  4994.7 2106.58
  4995.1 2107.08  5007.4 2108.02  5028.3 2107.87  5035.9 2108.85  5064.3 2110.69
  5120.3 2112.59  5142.2 2114.24  5148.8 2113.81  5205.8 2116.08  5291.2 2120.84
  5375.6 2124.66  5417.9 2128.17  5489.5 2137.47  5510.4 2139.07  5531.8 2139.24
#Mann=3,-1,0
  4708.7    0.07       0  4989.8    0.05       0  4995.1    0.07       0
Bank Sta=4989.8,4995.1
Exp/Cntr=0.3,0.1

Type RM Length L Ch R = 1,4262,443,443,443
BEGIN DESCRIPTION:
Stream0142 9.0
END DESCRIPTION:
XS GIS Cut Line= 3
      1802025.02     13916625.03      1802125.00     13916775.00
      1802524.97     13917124.97
#Sta/Elev= 30
  4815.4 2124.83  4880.0 2118.65  4916.0 2116.79  4952.1 2112.28  4959.6 2112.24
  4973.1 2109.44  4992.6 2107.04  4999.0 2107.04  5002.8 2104.80  5009.4 2105.11
  5021.0 2103.80  5021.4 2103.30  5026.3 2103.80  5052.1 2105.10  5115.7 2104.99
  5158.4 2106.05  5186.9 2107.63  5194.5 2108.87  5201.1 2108.75  5229.6 2111.72
  5250.5 2111.31  5258.1 2112.62  5264.7 2112.34  5279.0 2113.35  5385.3 2121.92
  5448.8 2129.90  5456.4 2131.67  5491.6 2136.25  5520.0 2137.89  5527.1 2137.57
#Mann=3,-1,0
  4815.4    0.07       0  5021.0    0.05       0  5026.3    0.07       0
Bank Sta=5021,5026.3
Exp/Cntr=0.3,0.1

Type RM Length L Ch R = 1,3819,473,473,473
BEGIN DESCRIPTION:
Stream0142 8.0
END DESCRIPTION:
XS GIS Cut Line= 3
      1801774.98     13916774.96      1801925.00     13917125.00
      1802274.96     13917374.97
#Sta/Elev= 30
  4619.2 2123.86  4633.8 2123.39  4680.9 2119.52  4749.8 2115.32  4771.6 2114.64
  4780.6 2113.61  4786.1 2114.14  4838.7 2110.50  4847.7 2110.68  4914.8 2104.67
  4945.6 2102.69  5003.1 2101.27  5049.2 2103.40  5072.5 2103.46  5093.4 2102.96
  5114.3 2100.33  5135.2 2102.26  5143.8 2103.82  5179.5 2103.84  5208.9 2102.77
  5229.8 2099.02  5233.3 2097.62  5233.7 2097.12  5238.6 2097.62  5244.6 2097.85
  5258.1 2101.46  5286.4 2117.20  5351.5 2133.16  5393.3 2137.44  5430.1 2139.54
#Mann=3,-1,0
  4619.2    0.07       0  5233.3    0.05       0  5238.6    0.07       0
Bank Sta=5233.3,5238.6
Exp/Cntr=0.3,0.1

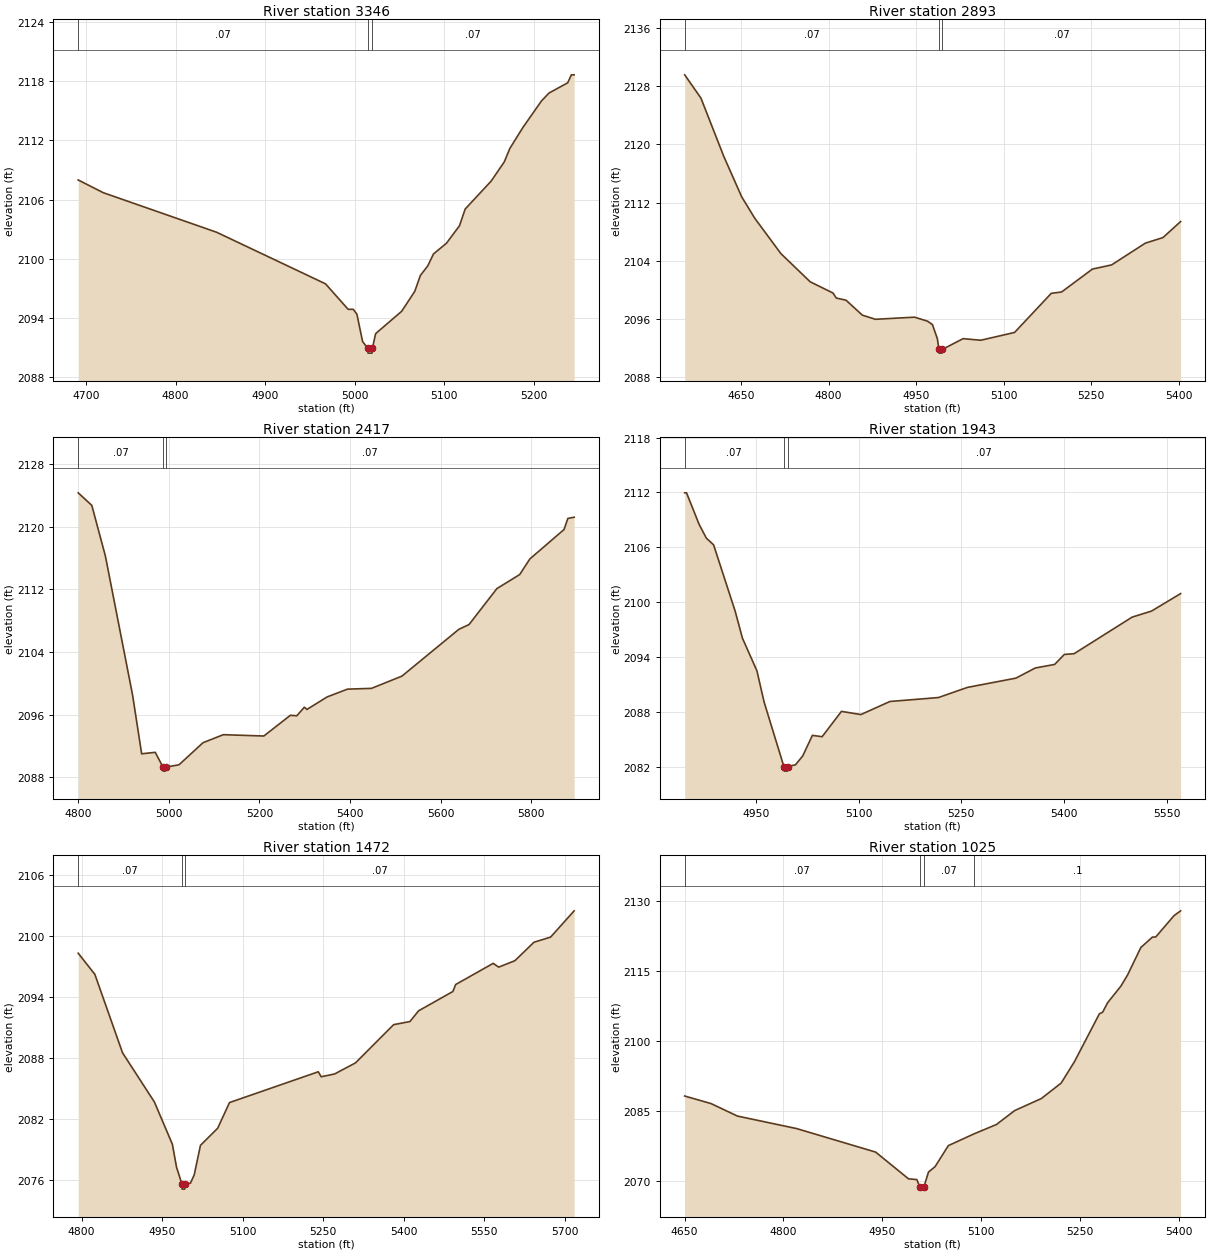
Type RM Length L Ch R = 1,3346,453,453,453
BEGIN DESCRIPTION:
Stream0142 7.0
END DESCRIPTION:
XS GIS Cut Line= 3
      1801575.00     13917124.99      1801625.00     13917425.00
      1801824.96     13917574.97
#Sta/Elev= 30
  4691.1 2107.99  4719.0 2106.70  4845.7 2102.68  4967.4 2097.44  4992.7 2094.85
  4998.4 2094.85  5002.5 2094.35  5008.8 2091.59  5014.4 2090.90  5014.9 2090.40
  5019.4 2090.40  5019.8 2090.90  5023.4 2092.38  5052.5 2094.65  5067.1 2096.67
  5073.4 2098.29  5081.7 2099.27  5088.0 2100.47  5102.5 2101.56  5117.1 2103.34
  5123.4 2105.03  5152.5 2107.88  5167.1 2109.82  5173.4 2111.20  5188.0 2113.33
  5208.8 2116.03  5217.1 2116.82  5238.0 2117.86  5242.1 2118.67  5245.2 2118.67
#Mann=3,-1,0
  4691.1    0.07       0  5014.4    0.05       0  5019.8    0.07       0
Bank Sta=5014.4,5019.8
Exp/Cntr=0.3,0.1

Type RM Length L Ch R = 1,2893,476,476,476
BEGIN DESCRIPTION:
Stream0142 6.0
END DESCRIPTION:
XS GIS Cut Line= 3
      1800875.03     13917425.02      1801275.00     13917625.00
      1801675.01     13917675.00
#Sta/Elev= 30
  4553.2 2129.55  4581.1 2126.35  4620.2 2118.35  4651.0 2112.78  4673.4 2109.84
  4718.1 2104.99  4768.4 2101.11  4807.5 2099.57  4813.1 2098.88  4829.9 2098.58
  4857.8 2096.53  4880.2 2095.96  4947.3 2096.25  4969.6 2095.70  4978.0 2095.23
  4986.4 2093.31  4989.2 2091.81  4989.7 2091.31  4994.3 2091.31  4994.7 2091.81
  5030.6 2093.30  5060.8 2093.08  5118.8 2094.15  5181.8 2099.53  5199.4 2099.71
  5252.3 2102.86  5285.1 2103.43  5343.0 2106.42  5373.3 2107.19  5403.5 2109.39
#Mann=3,-1,0
  4553.2    0.07       0  4989.2    0.05       0  4994.7    0.07       0
Bank Sta=4989.2,4994.7
Exp/Cntr=0.3,0.1

Type RM Length L Ch R = 1,2417,474,474,474
BEGIN DESCRIPTION:
Stream0142 5.0
END DESCRIPTION:
XS GIS Cut Line= 3
      1800875.00     13918025.00      1801075.00     13918025.00
      1801874.98     13917625.01
#Sta/Elev= 30
  4800.1 2124.32  4830.1 2122.72  4860.1 2116.25  4920.1 2098.51  4940.1 2091.02
  4970.1 2091.21  4987.3 2089.31  4987.8 2088.81  4992.4 2088.81  4992.8 2089.31
  5022.5 2089.62  5075.6 2092.44  5120.3 2093.46  5209.7 2093.29  5268.4 2095.94
  5282.4 2095.87  5299.2 2096.97  5304.8 2096.68  5349.5 2098.28  5394.2 2099.27
  5447.3 2099.37  5514.4 2100.93  5640.2 2106.91  5662.5 2107.51  5724.0 2112.10
  5774.3 2113.89  5796.7 2115.88  5872.2 2119.64  5880.6 2121.05  5894.5 2121.21
#Mann=3,-1,0
  4800.1    0.07       0  4987.3    0.05       0  4992.8    0.07       0
Bank Sta=4987.3,4992.8
Exp/Cntr=0.3,0.1

Type RM Length L Ch R = 1,1943,471,471,471
BEGIN DESCRIPTION:
Stream0142 4.0
END DESCRIPTION:
XS GIS Cut Line= 3
      1801124.98     13918475.01      1801275.00     13918425.00
      1801674.99     13918025.01
#Sta/Elev= 30
  4846.2 2111.96  4848.9 2111.96  4867.3 2108.51  4877.8 2107.01  4888.4 2106.28
  4920.0 2099.00  4930.5 2096.08  4951.6 2092.52  4962.2 2089.08  4991.0 2082.05
  4991.5 2081.55  4996.1 2081.55  4996.5 2082.05  5007.9 2082.24  5018.5 2083.21
  5032.6 2085.46  5046.8 2085.31  5075.0 2088.08  5103.3 2087.73  5145.8 2089.16
  5216.5 2089.59  5258.9 2090.70  5329.6 2091.71  5357.9 2092.82  5386.2 2093.21
  5400.3 2094.30  5414.5 2094.38  5499.3 2098.38  5527.6 2099.04  5570.0 2100.95
#Mann=3,-1,0
  4846.2    0.07       0  4991.0    0.05       0  4996.5    0.07       0
Bank Sta=4991,4996.5
Exp/Cntr=0.3,0.1

Type RM Length L Ch R = 1,1472,447,447,447
BEGIN DESCRIPTION:
Stream0142 3.0
END DESCRIPTION:
XS GIS Cut Line= 3
      1801374.95     13918825.01      1801575.00     13918775.00
      1801827.83     13918103.95
#Sta/Elev= 30
  4793.8 2098.30  4824.8 2096.22  4876.3 2088.50  4935.6 2083.66  4969.1 2079.50
  4976.8 2077.25  4986.9 2075.58  4987.3 2075.08  4992.0 2075.08  4992.4 2075.58
  5002.7 2075.66  5009.8 2076.49  5021.4 2079.39  5053.4 2081.07  5075.5 2083.60
  5240.8 2086.63  5246.1 2086.14  5271.0 2086.41  5309.9 2087.50  5381.1 2091.27
  5411.3 2091.57  5427.5 2092.63  5491.3 2094.53  5496.6 2095.22  5566.4 2097.30
  5576.6 2096.93  5606.8 2097.56  5642.3 2099.38  5673.2 2099.88  5717.1 2102.47
#Mann=3,-1,0
  4793.8    0.07       0  4986.9    0.05       0  4992.4    0.07       0
Bank Sta=4986.9,4992.4
Exp/Cntr=0.3,0.1

Type RM Length L Ch R = 1,1025,472,472,472
BEGIN DESCRIPTION:
Stream0142 2.0
END DESCRIPTION:
XS GIS Cut Line= 3
      1801524.97     13919075.00      1801875.00     13919075.00
      1802274.96     13919025.00
#Sta/Elev= 30
  4650.1 2088.17  4690.1 2086.55  4730.1 2083.87  4820.1 2081.18  4940.1 2076.13
  4990.1 2070.38  5002.6 2070.24  5007.1 2068.68  5007.6 2068.18  5012.9 2068.18
  5013.4 2068.68  5020.3 2071.83  5030.4 2073.02  5050.5 2077.52  5089.4 2080.04
  5123.6 2082.06  5151.3 2085.05  5191.6 2087.62  5221.8 2090.95  5242.0 2095.54
  5279.8 2105.81  5284.8 2106.17  5292.4 2108.21  5312.5 2111.76  5322.6 2114.14
  5342.8 2120.05  5360.4 2122.29  5365.4 2122.31  5393.2 2126.90  5403.2 2127.93
#Mann=4,-1,0
  4650.1    0.07       0  5007.1    0.05       0  5013.4    0.07       0
  5089.4     0.1       0
Bank Sta=5007.1,5013.4
Exp/Cntr=0.3,0.1

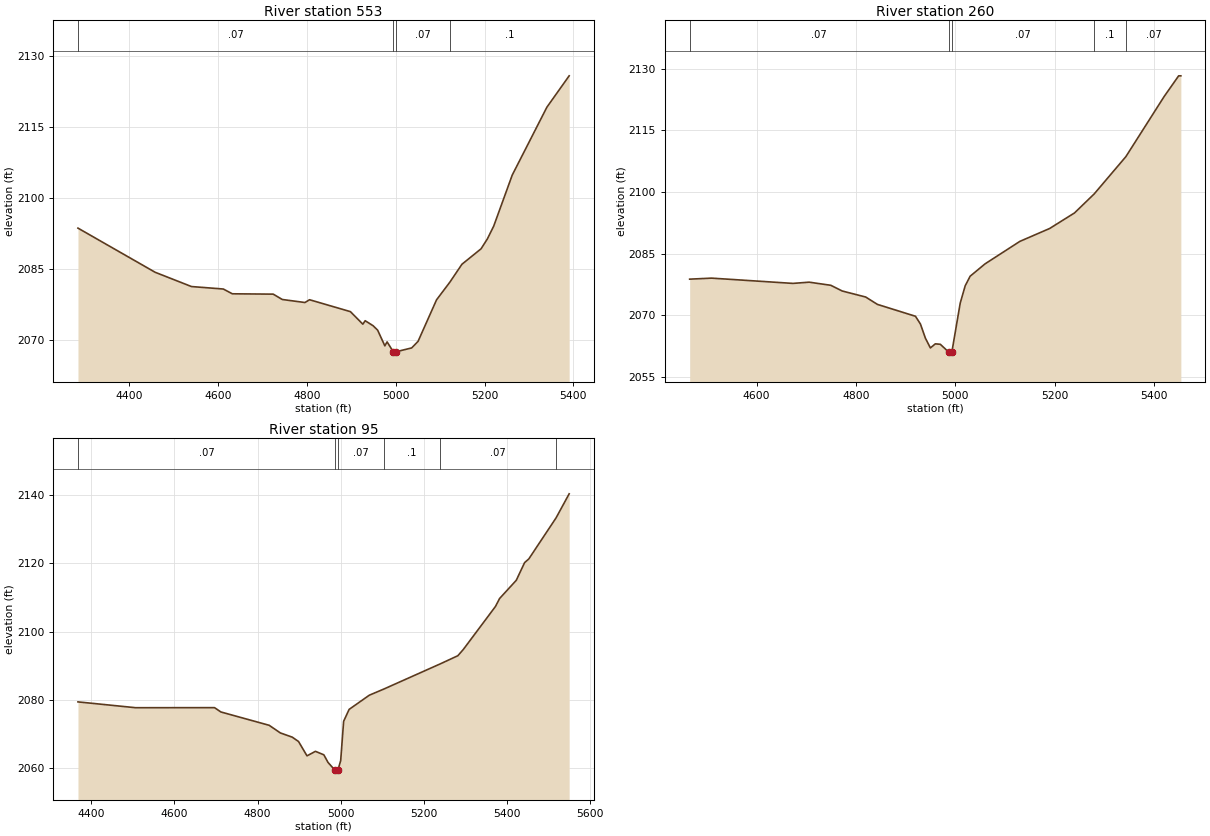
Type RM Length L Ch R = 1,553,293,293,293
BEGIN DESCRIPTION:
Stream0142 1.0
END DESCRIPTION:
XS GIS Cut Line= 3
      1801375.00     13919325.00      1802075.00     13919475.00
      1802325.00     13919175.00
#Sta/Elev= 30
  4284.1 2093.64  4458.0 2084.32  4539.8 2081.31  4611.4 2080.79  4631.8 2079.78
  4723.9 2079.71  4744.3 2078.58  4795.4 2077.94  4805.7 2078.53  4897.7 2076.02
  4925.8 2073.37  4931.0 2074.10  4948.9 2073.04  4959.1 2072.11  4975.3 2068.80
  4980.4 2069.63  4994.3 2067.55  4994.8 2067.05  5000.6 2067.55  5035.8 2068.36
  5050.1 2069.74  5091.8 2078.51  5121.8 2082.24  5149.0 2086.02  5192.0 2089.27
  5206.3 2091.37  5220.6 2094.08  5262.3 2104.84  5340.4 2119.17  5390.5 2125.78
#Mann=4,-1,0
  4284.1    0.07       0  4994.3    0.05       0  5000.6    0.07       0
  5121.8     0.1       0
Bank Sta=4994.3,5000.6
Exp/Cntr=0.3,0.1

Type RM Length L Ch R = 1,260,165,165,165
BEGIN DESCRIPTION:
Stream0142 0.1
END DESCRIPTION:
XS GIS Cut Line= 3
      1801674.11     13919570.57      1802052.49     13919732.93
      1802628.92     13919738.14
#Sta/Elev= 30
  4465.4 2078.83  4509.6 2079.08  4673.1 2077.80  4705.8 2078.10  4749.3 2077.34
  4772.4 2075.95  4819.5 2074.49  4843.1 2072.70  4919.7 2069.81  4929.7 2067.92
  4939.7 2064.48  4949.7 2062.12  4959.7 2063.11  4969.7 2063.00  4986.5 2061.11
  4987.0 2060.61  4992.4 2060.61  4992.9 2061.11  5009.7 2073.00  5019.7 2077.21
  5029.7 2079.55  5059.7 2082.55  5129.7 2088.01  5189.7 2091.15  5239.7 2094.93
  5279.2 2099.54  5343.0 2108.61  5419.7 2123.17  5449.2 2128.25  5453.6 2128.25
#Mann=5,-1,0
  4465.4    0.07       0  4986.5    0.05       0  4992.9    0.07       0
  5279.2     0.1       0  5343.0    0.07       0
Bank Sta=4986.5,4992.9
Exp/Cntr=0.3,0.1

Type RM Length L Ch R = 1,95,0,0,0
BEGIN DESCRIPTION:
Stream0142 0.0
END DESCRIPTION:
XS GIS Cut Line= 4
      1801617.48     13919620.13      1802034.40     13919875.88
      1802270.43     13919913.97      1802721.79     13919881.80
#Sta/Elev= 30
  4368.2 2079.37  4506.9 2077.66  4696.4 2077.68  4711.8 2076.41  4827.8 2072.50
  4854.7 2070.26  4883.2 2069.03  4898.4 2067.74  4918.7 2063.54  4939.0 2064.86
  4959.2 2063.84  4969.3 2061.60  4986.4 2059.26  4986.9 2058.76  4992.8 2059.26
  4999.7 2062.14  5006.8 2073.68  5020.0 2077.17  5068.5 2081.33  5103.7 2083.15
  5238.8 2090.51  5281.4 2092.92  5294.7 2094.79  5371.7 2107.36  5381.7 2109.71
  5421.8 2115.05  5441.8 2120.24  5451.9 2121.32  5517.2 2133.32  5548.9 2140.42
#Mann=6,-1,0
  4368.2    0.07       0  4986.4    0.05       0  4992.8    0.07       0
  5103.7     0.1       0  5238.8    0.07       0  5517.2     0.1       0
Bank Sta=4986.4,4992.8
Exp/Cntr=0.3,0.1

Chan Stop Cuts=-1