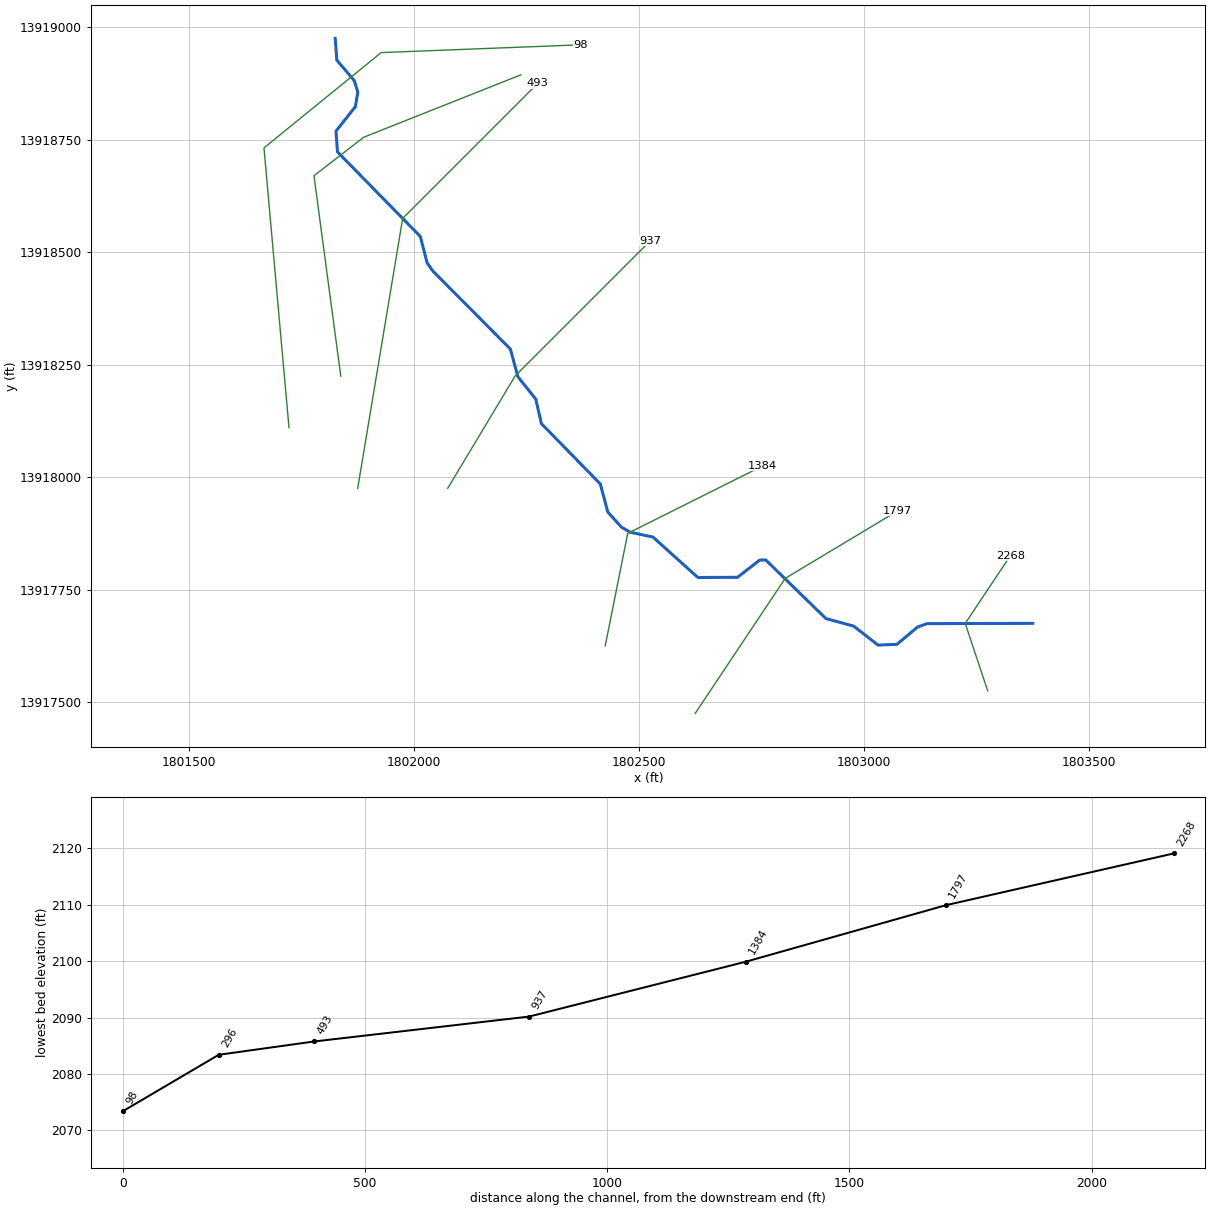
--- Stream0143.prj (project) ---

Proj Title=Stream0143 Base Level Engineering
Current Plan=p01
Default Exp/Contr=0.3,0.1
English Units
Geom File=g01
Flow File=f01
Plan File=p01
BEGIN DESCRIPTION:
Stream0143
END DESCRIPTION:

--- Stream0143.p01 (plan) ---

Plan Title=Multiple Run
Short Identifier=Multiple
Geom File=g01
Flow File=f01
Subcritical Flow
K Sum by GR= 0
Std Step Tol= 0.01
Critical Tol= 0.01
Num of Std Step Trials= 20
Max Error Tol= 0.3
Flow Tol Ratio= 0.001
Split Flow NTrial= 30
Split Flow Tol= 0.02
Split Flow Ratio= 0.02
Log Output Level= 0
Friction Slope Method= 1
Unsteady Friction Slope Method= 2
Unsteady Bridges Friction Slope Method= 1
Parabolic Critical Depth
Global Vel Dist=  1 , 1 , 1
Global Log Level= 0
CheckData=True
Encroach Param= -1, 0, 0, 0
BEGIN DESCRIPTION:
Multiple Run
END DESCRIPTION:

--- Stream0143.f01 (steady flow) ---

Flow Title=Multiple
Number of Profiles=7
Profile Names=10-year,25-year,50-year,1pct_min,100-year,1pct_plu,500-year
River Rch & RM= Stream0143,Reach-1,2268
     562     931    1272     842    1681    3354    2897
Boundary for River Rch & Prof#=Stream0143,Reach-1,1
Up Type=0
Dn Type=3
Dn Slope=0.005
Boundary for River Rch & Prof#=Stream0143,Reach-1,2
Up Type=0
Dn Type=3
Dn Slope=0.005
Boundary for River Rch & Prof#=Stream0143,Reach-1,3
Up Type=0
Dn Type=3
Dn Slope=0.005
Boundary for River Rch & Prof#=Stream0143,Reach-1,4
Up Type=0
Dn Type=3
Dn Slope=0.005
Boundary for River Rch & Prof#=Stream0143,Reach-1,5
Up Type=0
Dn Type=3
Dn Slope=0.005
Boundary for River Rch & Prof#=Stream0143,Reach-1,6
Up Type=0
Dn Type=3
Dn Slope=0.005
Boundary for River Rch & Prof#=Stream0143,Reach-1,7
Up Type=0
Dn Type=3
Dn Slope=0.005

--- Stream0143.g01 (geometry) ---

Geom Title=Existing Conditions

River Reach=Stream0143,Reach-1
Reach XY= 30
      1803375.00     13917675.00      1803140.21     13917674.46
      1803118.92     13917666.81      1803073.26     13917628.37
      1803031.11     13917626.80      1802977.19     13917668.82
      1802915.32     13917685.76      1802781.74     13917815.87
      1802768.47     13917815.71      1802719.11     13917777.37
      1802630.90     13917776.98      1802531.02     13917866.81
      1802480.87     13917877.46      1802461.44     13917888.49
      1802430.75     13917922.46      1802414.21     13917984.66
      1802283.14     13918118.94      1802270.81     13918173.26
      1802231.10     13918222.81      1802214.24     13918284.68
      1802041.65     13918458.33      1802028.98     13918476.65
      1802014.22     13918534.68      1801830.09     13918722.70
      1801826.81     13918768.88      1801869.59     13918822.80
      1801875.37     13918854.82      1801867.48     13918881.00
      1801828.69     13918926.49      1801825.00     13918975.00

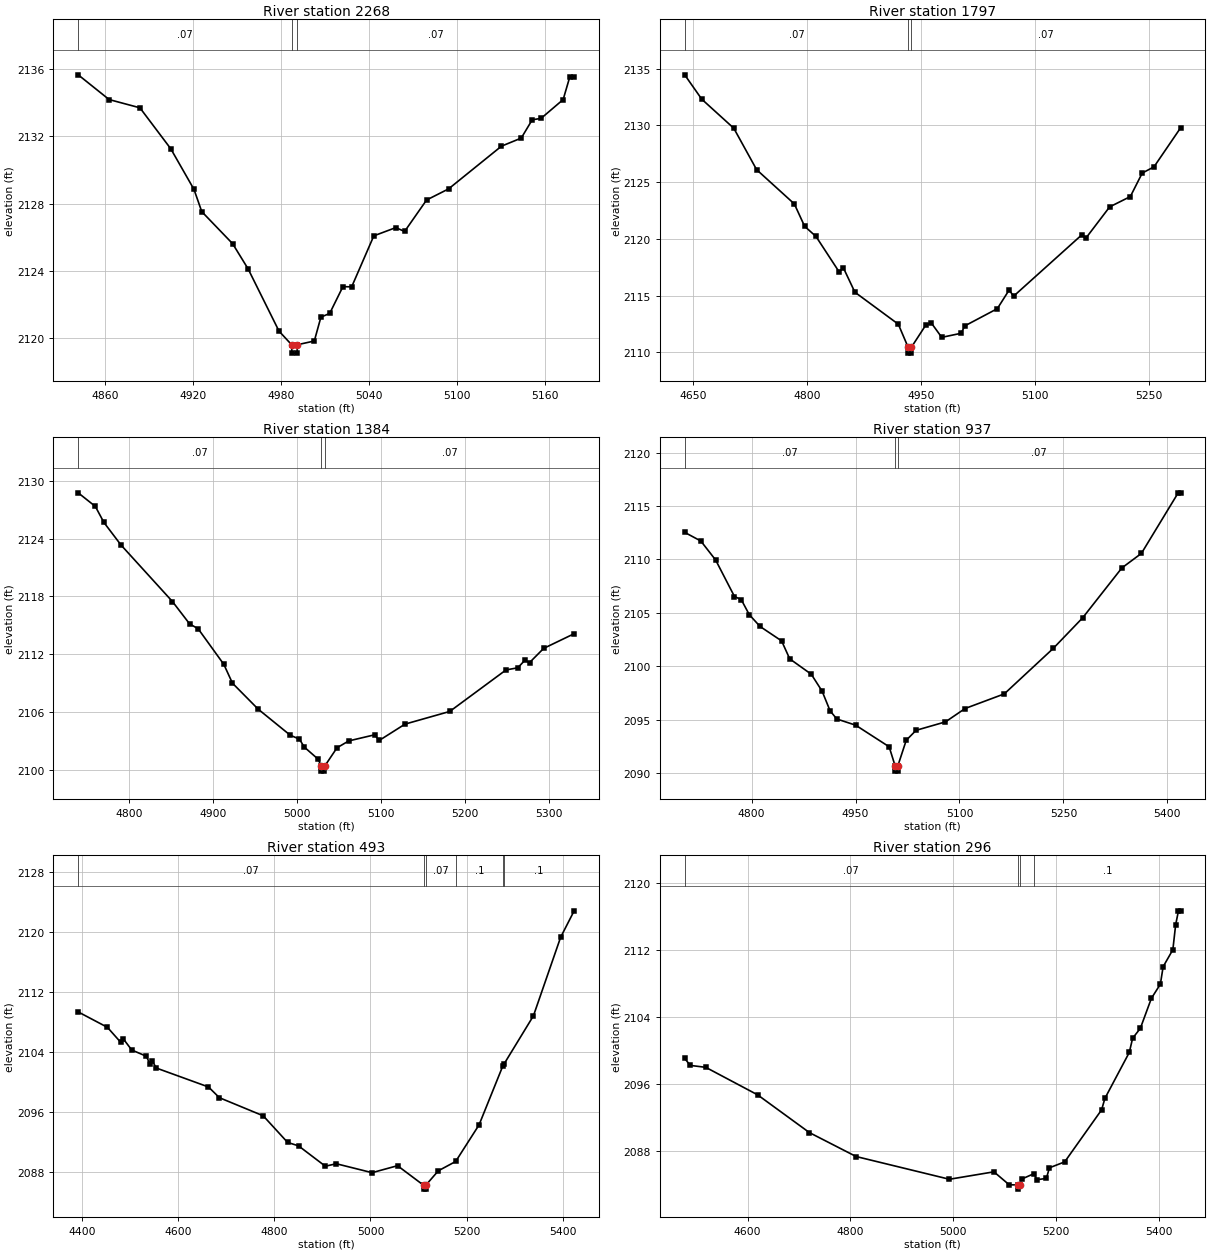
Type RM Length L Ch R = 1,2268,471,471,471
BEGIN DESCRIPTION:
Stream0143 5.0
END DESCRIPTION:
XS GIS Cut Line= 3
      1803274.99     13917525.02      1803225.00     13917675.00
      1803325.01     13917825.02
#Sta/Elev= 30
  4841.8 2135.66  4862.9 2134.19  4883.9 2133.70  4905.0 2131.26  4920.8 2128.85
  4926.1 2127.53  4947.2 2125.62  4957.7 2124.13  4978.8 2120.43  4987.4 2119.62
  4987.6 2119.12  4991.1 2119.12  4991.4 2119.62  5002.9 2119.84  5007.4 2121.26
  5013.4 2121.48  5022.4 2123.07  5028.4 2123.06  5043.5 2126.09  5058.5 2126.58
  5064.5 2126.35  5079.5 2128.22  5094.5 2128.88  5130.6 2131.42  5144.1 2131.90
  5151.6 2132.99  5157.6 2133.07  5172.7 2134.19  5177.2 2135.53  5180.2 2135.53
#Mann=3,-1,0
  4841.8    0.07       0  4987.4    0.05       0  4991.4    0.07       0
Bank Sta=4987.4,4991.4
Exp/Cntr=0.3,0.1

Type RM Length L Ch R = 1,1797,413,413,413
BEGIN DESCRIPTION:
Stream0143 4.0
END DESCRIPTION:
XS GIS Cut Line= 3
      1802625.01     13917475.01      1802825.00     13917775.00
      1803075.01     13917925.01
#Sta/Elev= 30
  4639.1 2134.46  4661.6 2132.31  4703.7 2129.75  4733.7 2126.10  4783.3 2123.08
  4796.8 2121.11  4811.8 2120.21  4841.9 2117.12  4847.9 2117.43  4862.9 2115.30
  4920.0 2112.48  4933.0 2110.43  4933.3 2109.93  4936.8 2109.93  4937.0 2110.43
  4956.1 2112.40  4963.6 2112.57  4977.1 2111.32  5002.6 2111.68  5007.4 2112.33
  5050.2 2113.85  5065.7 2115.49  5071.6 2114.95  5161.0 2120.34  5166.8 2120.08
  5197.9 2122.82  5225.1 2123.73  5240.7 2125.80  5256.2 2126.35  5291.2 2129.79
#Mann=3,-1,0
  4639.1    0.07       0  4933.0    0.05       0  4937.0    0.07       0
Bank Sta=4933,4937
Exp/Cntr=0.3,0.1

Type RM Length L Ch R = 1,1384,447,447,447
BEGIN DESCRIPTION:
Stream0143 3.0
END DESCRIPTION:
XS GIS Cut Line= 3
      1802424.99     13917624.97      1802475.00     13917875.00
      1802775.00     13918025.00
#Sta/Elev= 30
  4739.1 2128.73  4759.5 2127.32  4769.7 2125.66  4790.1 2123.32  4851.3 2117.47
  4871.7 2115.16  4881.9 2114.65  4912.5 2110.96  4922.7 2109.02  4953.3 2106.33
  4991.5 2103.63  5002.5 2103.22  5008.1 2102.41  5024.8 2101.14  5028.4 2100.41
  5028.7 2099.91  5032.2 2099.91  5032.4 2100.41  5047.2 2102.33  5061.2 2103.04
  5091.9 2103.67  5097.5 2103.09  5128.2 2104.78  5181.4 2106.09  5248.4 2110.39
  5262.4 2110.61  5270.8 2111.39  5276.4 2111.15  5293.2 2112.62  5329.5 2114.14
#Mann=3,-1,0
  4739.1    0.07       0  5028.4    0.05       0  5032.4    0.07       0
Bank Sta=5028.4,5032.4
Exp/Cntr=0.3,0.1

Type RM Length L Ch R = 1,937,444,444,444
BEGIN DESCRIPTION:
Stream0143 2.0
END DESCRIPTION:
XS GIS Cut Line= 3
      1802075.00     13917975.00      1802225.00     13918225.00
      1802524.99     13918524.99
#Sta/Elev= 30
  4703.4 2112.54  4726.7 2111.73  4748.1 2109.95  4775.3 2106.53  4785.0 2106.25
  4796.7 2104.83  4812.2 2103.73  4843.3 2102.38  4855.0 2100.70  4886.1 2099.26
  4901.7 2097.68  4913.3 2095.83  4923.0 2095.07  4950.2 2094.49  4998.5 2092.47
  5007.1 2090.69  5007.3 2090.19  5010.8 2090.19  5011.1 2090.69  5023.2 2093.08
  5037.4 2094.01  5079.8 2094.80  5108.1 2096.05  5164.7 2097.42  5235.4 2101.68
  5277.8 2104.54  5334.4 2109.21  5362.6 2110.57  5415.7 2116.24  5419.2 2116.24
#Mann=3,-1,0
  4703.4    0.07       0  5007.1    0.05       0  5011.1    0.07       0
Bank Sta=5007.1,5011.1
Exp/Cntr=0.3,0.1

Type RM Length L Ch R = 1,493,197,197,197
BEGIN DESCRIPTION:
Stream0143 1.0
END DESCRIPTION:
XS GIS Cut Line= 3
      1801875.00     13917975.00      1801975.00     13918575.00
      1802274.97     13918874.97
#Sta/Elev= 30
  4391.5 2109.36  4452.3 2107.31  4480.2 2105.30  4485.3 2105.78  4503.0 2104.29
  4533.4 2103.46  4541.0 2102.39  4546.1 2102.83  4553.7 2101.90  4662.7 2099.37
  4685.5 2097.94  4776.7 2095.53  4827.4 2091.99  4850.2 2091.53  4906.0 2088.82
  4928.8 2089.15  5003.3 2087.96  5056.3 2088.89  5110.9 2086.27  5111.2 2085.77
  5114.7 2085.77  5114.9 2086.27  5141.2 2088.21  5177.3 2089.45  5226.0 2094.32
  5275.7 2102.20  5277.5 2102.37  5339.2 2108.84  5395.8 2119.29  5424.0 2122.82
#Mann=6,-1,0
  4391.5    0.07       0  5110.9    0.05       0  5114.9    0.07       0
  5177.3     0.1       0  5275.7    0.07       0  5277.5     0.1       0
Bank Sta=5110.9,5114.9
Exp/Cntr=0.3,0.1

Type RM Length L Ch R = 1,296,198,198,198
BEGIN DESCRIPTION:
Stream0143 0.0
END DESCRIPTION:
XS GIS Cut Line= 4
      1801837.44     13918224.34      1801777.87     13918669.67
      1801888.39     13918755.21      1802237.88     13918894.02
#Sta/Elev= 30
  4477.4 2099.05  4488.2 2098.21  4518.4 2097.98  4619.3 2094.69  4720.2 2090.17
  4811.0 2087.31  4992.6 2084.59  5079.2 2085.48  5108.9 2083.93  5125.4 2083.91
  5125.6 2083.41  5129.4 2083.91  5133.2 2084.61  5157.0 2085.26  5162.9 2084.54
  5181.2 2084.69  5187.2 2085.96  5216.9 2086.67  5288.8 2092.90  5295.1 2094.26
  5342.6 2099.76  5349.1 2101.46  5364.1 2102.64  5385.6 2106.23  5403.1 2107.93
  5408.5 2110.02  5427.4 2112.05  5432.8 2115.02  5438.3 2116.70  5442.5 2116.70
#Mann=4,-1,0
  4477.4    0.07       0  5125.4    0.05       0  5129.4    0.07       0
  5157.0     0.1       0
Bank Sta=5125.4,5129.4
Exp/Cntr=0.3,0.1

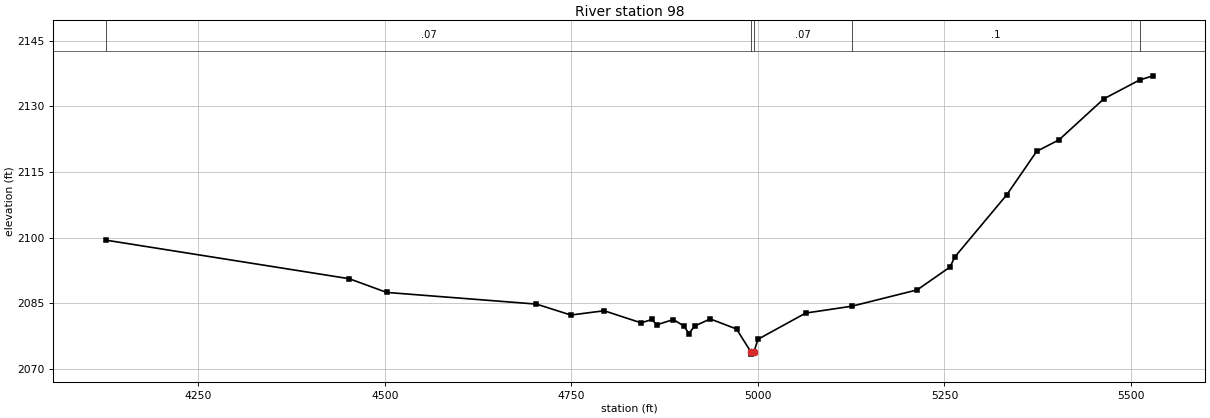
Type RM Length L Ch R = 1,98,0,0,0
BEGIN DESCRIPTION:
Stream0143 0.1
END DESCRIPTION:
XS GIS Cut Line= 4
      1801722.33     13918109.96      1801666.77     13918731.52
      1801927.19     13918943.32      1802370.84     13918960.65
#Sta/Elev= 30
  4125.9 2099.45  4452.2 2090.63  4502.4 2087.50  4703.2 2084.83  4749.2 2082.33
  4793.9 2083.31  4843.5 2080.54  4857.8 2081.32  4864.3 2080.09  4886.6 2081.30
  4900.9 2079.81  4907.4 2078.10  4915.2 2079.82  4936.1 2081.44  4971.3 2079.14
  4990.6 2073.90  4990.8 2073.40  4994.6 2073.90  5000.1 2076.80  5064.0 2082.78
  5125.9 2084.35  5213.5 2088.08  5257.6 2093.32  5263.6 2095.54  5333.6 2109.82
  5373.6 2119.73  5403.7 2122.38  5463.7 2131.74  5511.7 2136.05  5529.6 2136.99
#Mann=5,-1,0
  4125.9    0.07       0  4990.6    0.05       0  4994.6    0.07       0
  5125.9     0.1       0  5511.7    0.07       0
Bank Sta=4990.6,4994.6
Exp/Cntr=0.3,0.1

Chan Stop Cuts=-1