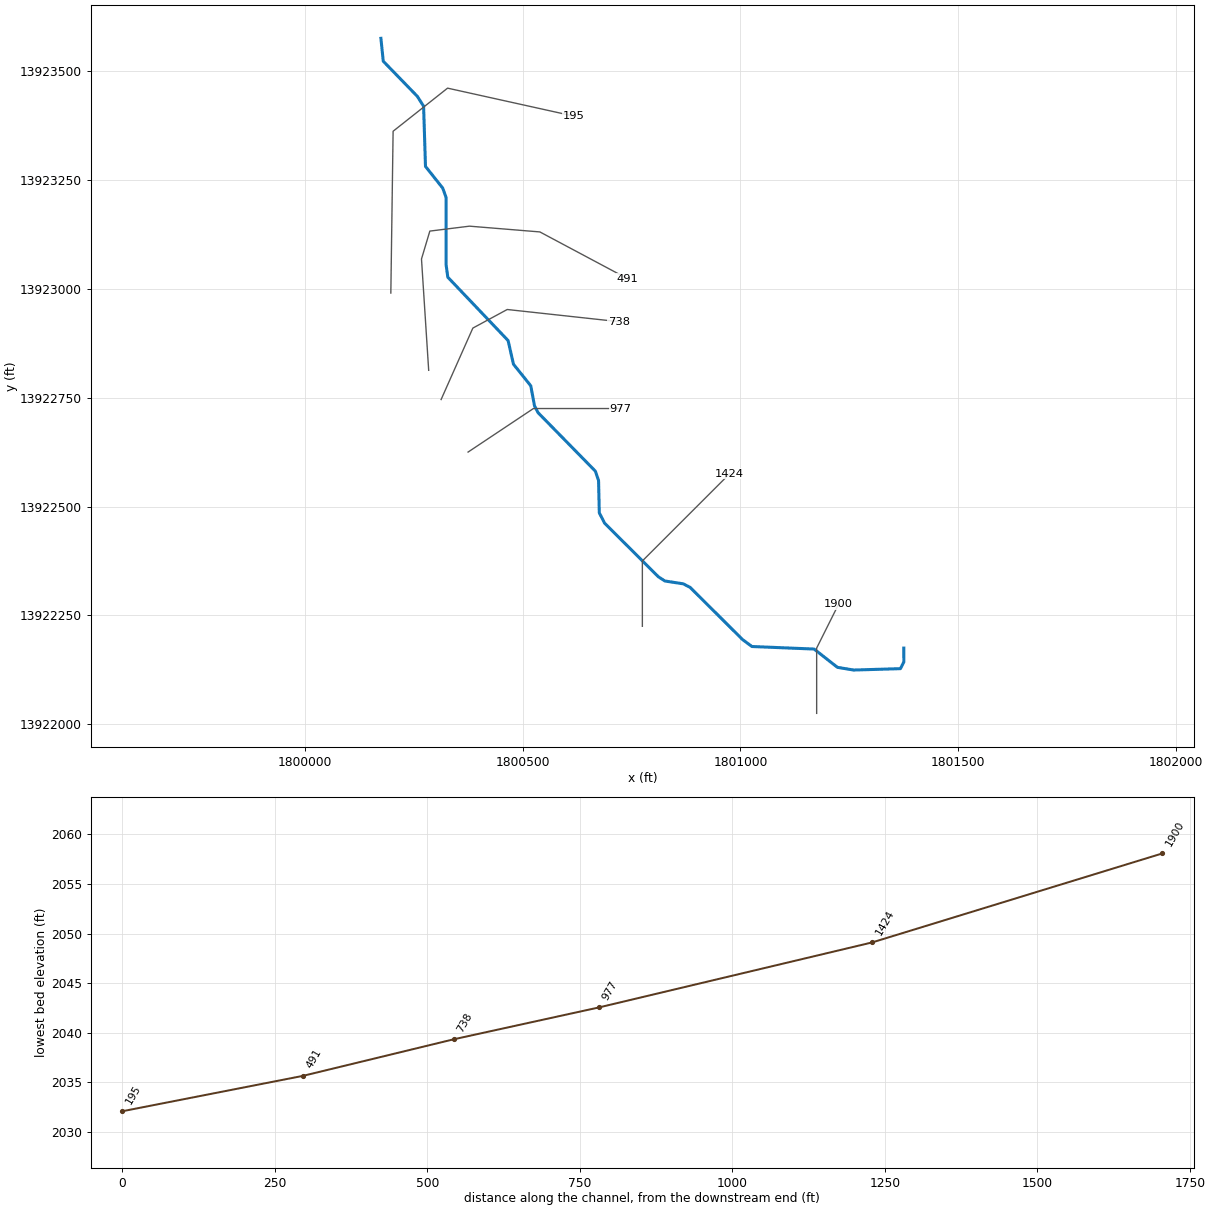
--- Stream0145.prj (project) ---

Proj Title=Stream0145 Base Level Engineering
Current Plan=p01
Default Exp/Contr=0.3,0.1
English Units
Geom File=g01
Flow File=f01
Plan File=p01
BEGIN DESCRIPTION:
Stream0145
END DESCRIPTION:

--- Stream0145.p01 (plan) ---

Plan Title=Multiple Run
Short Identifier=Multiple
Geom File=g01
Flow File=f01
Subcritical Flow
K Sum by GR= 0
Std Step Tol= 0.01
Critical Tol= 0.01
Num of Std Step Trials= 20
Max Error Tol= 0.3
Flow Tol Ratio= 0.001
Split Flow NTrial= 30
Split Flow Tol= 0.02
Split Flow Ratio= 0.02
Log Output Level= 0
Friction Slope Method= 1
Unsteady Friction Slope Method= 2
Unsteady Bridges Friction Slope Method= 1
Parabolic Critical Depth
Global Vel Dist=  1 , 1 , 1
Global Log Level= 0
CheckData=True
Encroach Param= -1, 0, 0, 0
BEGIN DESCRIPTION:
Multiple Run
END DESCRIPTION:

--- Stream0145.f01 (steady flow) ---

Flow Title=Multiple
Number of Profiles=7
Profile Names=10-year,25-year,50-year,1pct_min,100-year,1pct_plu,500-year
River Rch & RM= Stream0145,Reach-1,1900
     645    1076    1476     982    1959    3908    3403
Boundary for River Rch & Prof#=Stream0145,Reach-1,1
Up Type=0
Dn Type=3
Dn Slope=0.005
Boundary for River Rch & Prof#=Stream0145,Reach-1,2
Up Type=0
Dn Type=3
Dn Slope=0.005
Boundary for River Rch & Prof#=Stream0145,Reach-1,3
Up Type=0
Dn Type=3
Dn Slope=0.005
Boundary for River Rch & Prof#=Stream0145,Reach-1,4
Up Type=0
Dn Type=3
Dn Slope=0.005
Boundary for River Rch & Prof#=Stream0145,Reach-1,5
Up Type=0
Dn Type=3
Dn Slope=0.005
Boundary for River Rch & Prof#=Stream0145,Reach-1,6
Up Type=0
Dn Type=3
Dn Slope=0.005
Boundary for River Rch & Prof#=Stream0145,Reach-1,7
Up Type=0
Dn Type=3
Dn Slope=0.005

--- Stream0145.g01 (geometry) ---

Geom Title=Existing Conditions

River Reach=Stream0145,Reach-1
Reach XY= 30
      1801375.00     13922175.00      1801375.10     13922143.04
      1801367.29     13922127.69      1801259.86     13922124.52
      1801222.67     13922130.74      1801169.06     13922172.73
      1801026.47     13922178.54      1801004.84     13922194.61
      1800884.68     13922314.22      1800868.95     13922322.46
      1800826.65     13922328.98      1800811.79     13922338.63
      1800688.40     13922461.70      1800676.17     13922485.48
      1800674.47     13922559.78      1800667.14     13922581.17
      1800535.77     13922715.32      1800527.50     13922731.04
      1800518.90     13922777.19      1800479.19     13922826.74
      1800466.86     13922881.06      1800328.54     13923026.46
      1800324.57     13923054.82      1800324.48     13923209.78
      1800316.86     13923231.06      1800277.27     13923280.94
      1800272.93     13923419.14      1800258.56     13923441.76
      1800180.33     13923522.49      1800175.00     13923575.00

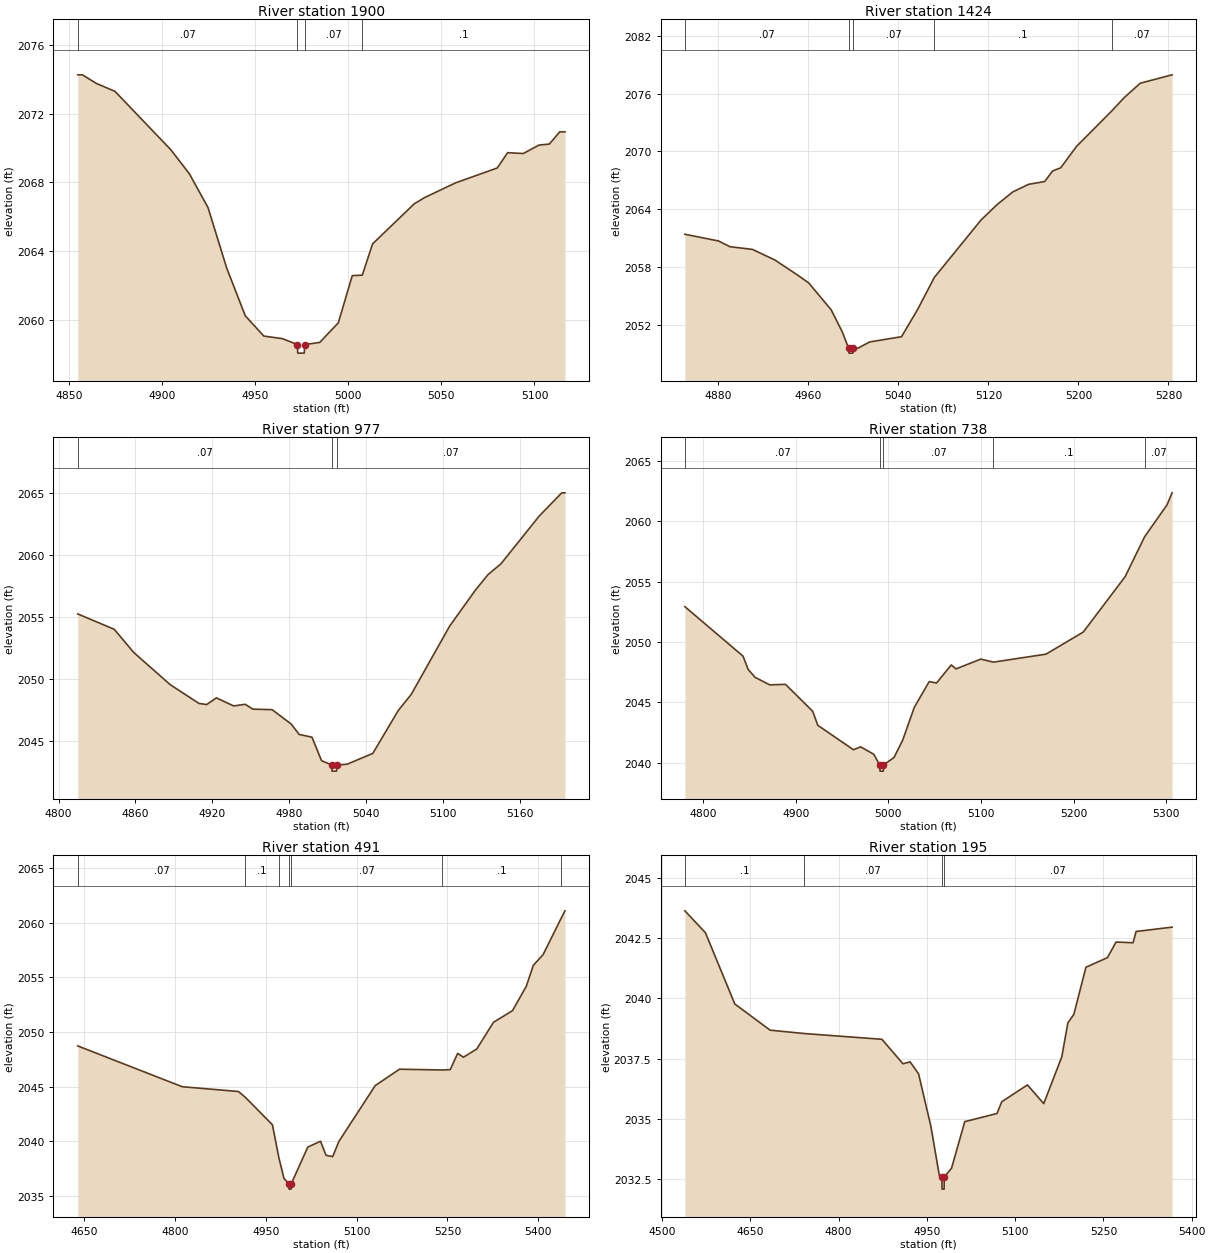
Type RM Length L Ch R = 1,1900,476,476,476
BEGIN DESCRIPTION:
Stream0145 3.0
END DESCRIPTION:
XS GIS Cut Line= 3
      1801175.00     13922025.02      1801175.00     13922175.00
      1801225.01     13922275.02
#Sta/Elev= 30
  4854.6 2074.25  4857.1 2074.25  4864.6 2073.75  4874.6 2073.29  4904.6 2069.90
  4914.6 2068.50  4924.6 2066.54  4934.6 2063.04  4944.6 2060.26  4954.6 2059.08
  4964.6 2058.93  4972.6 2058.59  4972.8 2058.09  4976.3 2058.09  4976.6 2058.59
  4984.6 2058.71  4994.6 2059.85  5002.1 2062.59  5007.5 2062.62  5013.0 2064.43
  5035.3 2066.75  5040.9 2067.12  5057.7 2067.98  5080.0 2068.84  5085.6 2069.73
  5094.0 2069.68  5102.4 2070.17  5108.0 2070.23  5113.6 2070.94  5116.4 2070.94
#Mann=4,-1,0
  4854.6    0.07       0  4972.6    0.05       0  4976.6    0.07       0
  5007.5     0.1       0
Bank Sta=4972.6,4976.6
Exp/Cntr=0.3,0.1

Type RM Length L Ch R = 1,1424,447,447,447
BEGIN DESCRIPTION:
Stream0145 2.0
END DESCRIPTION:
XS GIS Cut Line= 3
      1800775.00     13922224.97      1800775.00     13922375.00
      1800975.02     13922575.02
#Sta/Elev= 30
  4850.3 2061.42  4880.3 2060.72  4890.3 2060.13  4910.3 2059.85  4930.3 2058.75
  4950.3 2057.20  4960.3 2056.38  4980.3 2053.59  4990.3 2051.27  4995.8 2049.60
  4996.1 2049.10  4999.6 2049.10  4999.8 2049.60  5003.9 2049.60  5014.5 2050.26
  5042.8 2050.80  5056.9 2053.58  5072.0 2056.95  5113.5 2062.90  5127.6 2064.48
  5141.7 2065.81  5155.9 2066.60  5170.0 2066.88  5177.1 2067.98  5184.2 2068.30
  5198.3 2070.52  5229.8 2074.22  5240.7 2075.58  5254.9 2077.07  5283.2 2077.94
#Mann=5,-1,0
  4850.3    0.07       0  4995.8    0.05       0  4999.8    0.07       0
  5072.0     0.1       0  5229.8    0.07       0
Bank Sta=4995.8,4999.8
Exp/Cntr=0.3,0.1

Type RM Length L Ch R = 1,977,239,239,239
BEGIN DESCRIPTION:
Stream0145 1.0
END DESCRIPTION:
XS GIS Cut Line= 3
      1800375.01     13922625.00      1800525.00     13922725.00
      1800725.03     13922725.00
#Sta/Elev= 30
  4815.0 2055.23  4843.5 2053.99  4858.6 2052.13  4887.1 2049.53  4909.6 2048.01
  4915.6 2047.92  4923.2 2048.46  4936.7 2047.81  4945.7 2047.94  4951.7 2047.55
  4966.7 2047.51  4981.7 2046.34  4987.8 2045.51  4997.8 2045.29  5005.3 2043.39
  5013.3 2043.05  5013.5 2042.55  5017.0 2042.55  5017.3 2043.05  5025.3 2043.11
  5045.3 2043.98  5065.3 2047.46  5075.3 2048.74  5105.3 2054.25  5125.3 2057.14
  5135.3 2058.41  5145.3 2059.27  5175.3 2063.14  5192.8 2065.00  5195.3 2065.00
#Mann=3,-1,0
  4815.0    0.07       0  5013.3    0.05       0  5017.3    0.07       0
Bank Sta=5013.3,5017.3
Exp/Cntr=0.3,0.1

Type RM Length L Ch R = 1,738,247,247,247
BEGIN DESCRIPTION:
Stream0145 0.1
END DESCRIPTION:
XS GIS Cut Line= 4
      1800313.13     13922745.63      1800385.97     13922909.69
      1800464.85     13922952.37      1800720.35     13922924.50
#Sta/Elev= 30
  4780.2 2052.93  4843.1 2048.83  4848.5 2047.74  4856.1 2047.08  4871.8 2046.46
  4888.9 2046.50  4918.3 2044.27  4923.8 2043.11  4962.3 2041.09  4970.0 2041.33
  4984.2 2040.72  4990.7 2039.82  4991.0 2039.32  4994.5 2039.32  4994.7 2039.82
  5006.1 2040.45  5015.5 2041.89  5028.0 2044.60  5044.1 2046.73  5052.0 2046.61
  5067.9 2048.11  5073.0 2047.78  5099.8 2048.59  5113.5 2048.34  5170.3 2049.00
  5210.5 2050.83  5255.7 2055.41  5276.8 2058.72  5301.0 2061.36  5306.4 2062.35
#Mann=5,-1,0
  4780.2    0.07       0  4990.7    0.05       0  4994.7    0.07       0
  5113.5     0.1       0  5276.8    0.07       0
Bank Sta=4990.7,4994.7
Exp/Cntr=0.3,0.1

Type RM Length L Ch R = 1,491,296,296,296
BEGIN DESCRIPTION:
Stream0145 0.0
END DESCRIPTION:
XS GIS Cut Line= 6
      1800284.61     13922812.74      1800268.10     13923068.37
      1800287.26     13923132.41      1800378.23     13923143.72
      1800539.77     13923130.49      1800741.51     13923022.89
#Sta/Elev= 30
  4638.9 2048.73  4811.5 2045.00  4904.5 2044.56  4915.7 2044.04  4960.7 2041.52
  4971.5 2038.47  4979.8 2036.60  4987.9 2036.13  4988.1 2035.63  4991.6 2035.63
  4991.9 2036.13  5019.2 2039.48  5040.2 2040.01  5049.4 2038.72  5060.4 2038.61
  5070.4 2039.98  5130.6 2045.10  5170.7 2046.60  5240.7 2046.53  5254.6 2046.56
  5266.9 2048.05  5276.5 2047.70  5298.5 2048.45  5326.1 2050.89  5357.6 2051.96
  5380.3 2054.18  5392.0 2056.10  5408.3 2057.10  5438.0 2060.41  5444.3 2061.09
#Mann=7,-1,0
  4638.9    0.07       0  4915.7     0.1       0  4971.5    0.07       0
  4987.9    0.05       0  4991.9    0.07       0  5240.7     0.1       0
  5438.0    0.07       0
Bank Sta=4987.9,4991.9
Exp/Cntr=0.3,0.1

Type RM Length L Ch R = 1,195,0,0,0
BEGIN DESCRIPTION:
Stream0145 0.3
END DESCRIPTION:
XS GIS Cut Line= 4
      1800197.76     13922990.14      1800202.97     13923361.67
      1800327.97     13923460.63      1800617.94     13923396.38
#Sta/Elev= 30
  4538.7 2043.65  4573.6 2042.74  4623.6 2039.77  4683.6 2038.68  4741.5 2038.54
  4873.6 2038.30  4909.4 2037.28  4921.5 2037.36  4935.9 2036.86  4956.7 2034.69
  4971.1 2032.64  4975.5 2032.56  4975.8 2032.06  4979.3 2032.06  4979.5 2032.56
  4991.9 2032.93  5014.4 2034.87  5069.2 2035.21  5077.3 2035.70  5120.9 2036.40
  5148.6 2035.62  5179.3 2037.57  5189.6 2038.98  5199.8 2039.34  5220.3 2041.30
  5256.8 2041.70  5271.5 2042.35  5300.4 2042.32  5305.6 2042.79  5366.7 2042.97
#Mann=4,-1,0
  4538.7     0.1       0  4741.5    0.07       0  4975.5    0.05       0
  4979.5    0.07       0
Bank Sta=4975.5,4979.5
Exp/Cntr=0.3,0.1

Chan Stop Cuts=-1