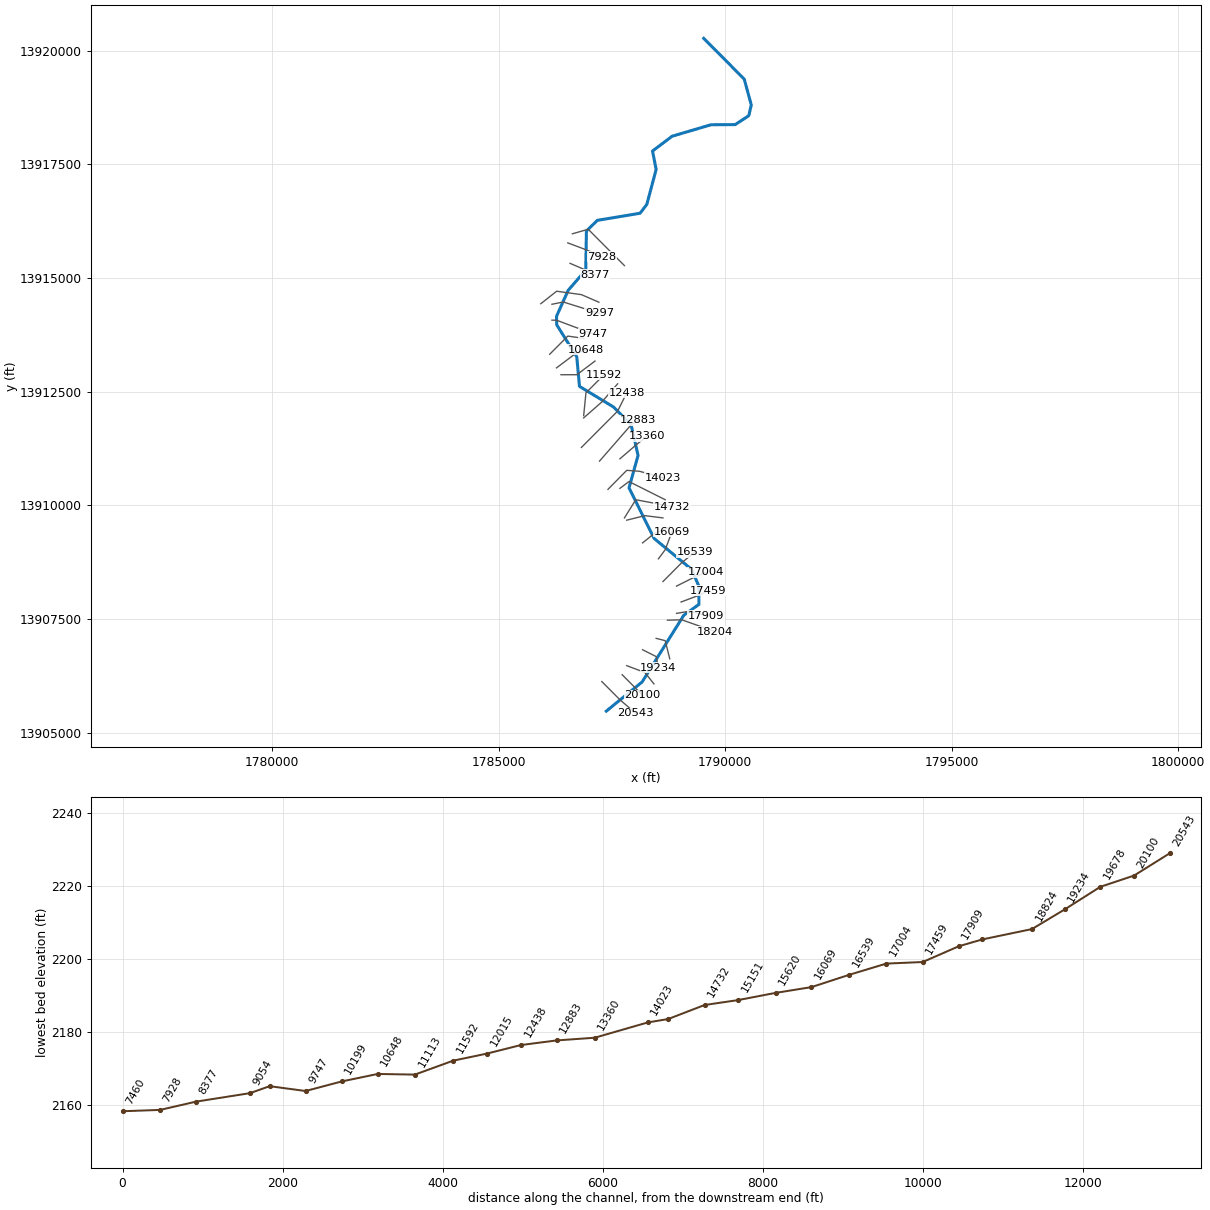
--- Stream0146.prj (project) ---

Proj Title=Stream0146 Base Level Engineering
Current Plan=p01
Default Exp/Contr=0.3,0.1
English Units
Geom File=g01
Flow File=f01
Plan File=p01
BEGIN DESCRIPTION:
Stream0146
END DESCRIPTION:

--- Stream0146.p01 (plan) ---

Plan Title=Multiple Run
Short Identifier=Multiple
Geom File=g01
Flow File=f01
Subcritical Flow
K Sum by GR= 0
Std Step Tol= 0.01
Critical Tol= 0.01
Num of Std Step Trials= 20
Max Error Tol= 0.3
Flow Tol Ratio= 0.001
Split Flow NTrial= 30
Split Flow Tol= 0.02
Split Flow Ratio= 0.02
Log Output Level= 0
Friction Slope Method= 1
Unsteady Friction Slope Method= 2
Unsteady Bridges Friction Slope Method= 1
Parabolic Critical Depth
Global Vel Dist=  1 , 1 , 1
Global Log Level= 0
CheckData=True
Encroach Param= -1, 0, 0, 0
BEGIN DESCRIPTION:
Multiple Run
END DESCRIPTION:

--- Stream0146.f01 (steady flow) ---

Flow Title=Multiple
Number of Profiles=7
Profile Names=10-year,25-year,50-year,1pct_min,100-year,1pct_plu,500-year
River Rch & RM= Stream0146,Reach-1,20543
    1249    2138    2984    2010    4010    8000    7162
River Rch & RM= Stream0146,Reach-1,18204
    2265    4005    5709    3918    7817   15597   14520
River Rch & RM= Stream0146,Reach-1,12015
    2641    4692    6712    4619    9216   18389   17214
River Rch & RM= Stream0146,Reach-1,8377
    2902    5163    7391    5086   10149   20249   18951
River Rch & RM= Stream0146,Reach-1,3299
    3220    5756    8267    5706   11385   22715   21387
Boundary for River Rch & Prof#=Stream0146,Reach-1,1
Up Type=0
Dn Type=3
Dn Slope=0.005
Boundary for River Rch & Prof#=Stream0146,Reach-1,2
Up Type=0
Dn Type=3
Dn Slope=0.005
Boundary for River Rch & Prof#=Stream0146,Reach-1,3
Up Type=0
Dn Type=3
Dn Slope=0.005
Boundary for River Rch & Prof#=Stream0146,Reach-1,4
Up Type=0
Dn Type=3
Dn Slope=0.005
Boundary for River Rch & Prof#=Stream0146,Reach-1,5
Up Type=0
Dn Type=3
Dn Slope=0.005
Boundary for River Rch & Prof#=Stream0146,Reach-1,6
Up Type=0
Dn Type=3
Dn Slope=0.005
Boundary for River Rch & Prof#=Stream0146,Reach-1,7
Up Type=0
Dn Type=3
Dn Slope=0.005

--- Stream0146.g01 (geometry) ---

Geom Title=Existing Conditions

River Reach=Stream0146,Reach-1
Reach XY= 30
      1787375.00     13905475.00      1788164.48     13906115.21
      1789085.62     13907585.01      1789419.54     13907822.55
      1789417.24     13908224.92      1789255.23     13908595.13
      1788430.52     13909272.57      1787876.05     13910385.44
      1788075.29     13911099.88      1787921.39     13911773.50
      1787534.68     13912164.24      1786782.76     13912618.79
      1786722.76     13913269.07      1786280.46     13913972.55
      1786275.51     13914159.79      1786532.70     13914731.47
      1786921.25     13915176.55      1786935.48     13916034.80
      1787176.47     13916271.46      1788119.33     13916426.98
      1788269.16     13916622.71      1788474.51     13917390.22
      1788394.52     13917795.50      1788826.50     13918121.38
      1789685.50     13918373.80      1790219.48     13918377.34
      1790519.18     13918572.69      1790574.49     13918809.78
      1790419.16     13919377.29      1789525.00     13920275.00

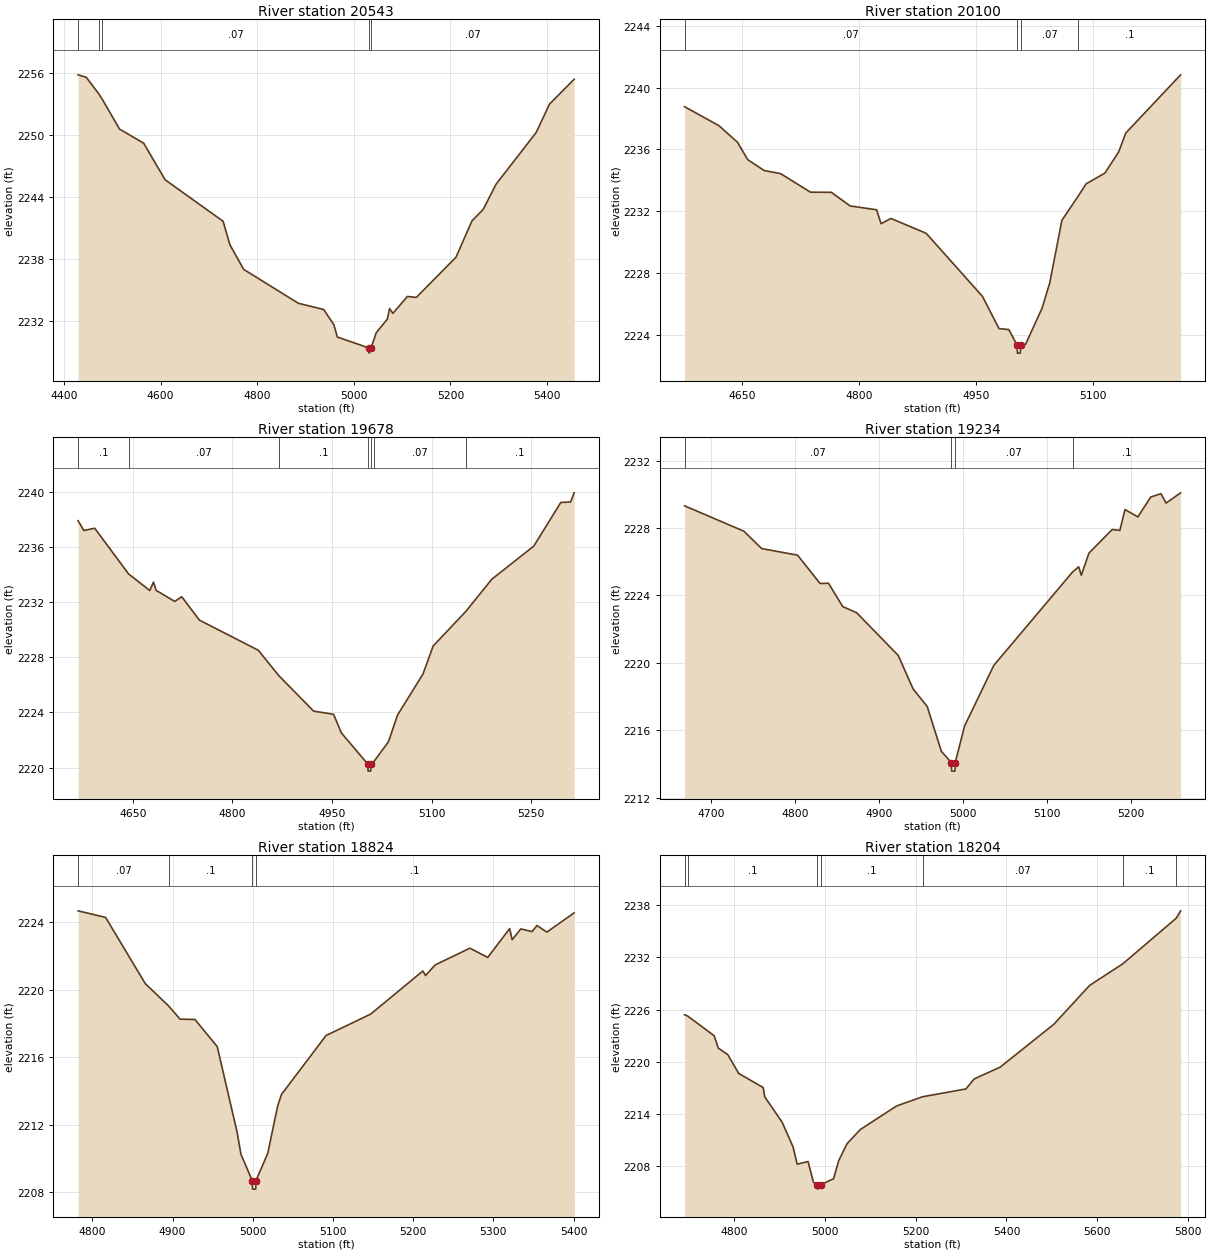
Type RM Length L Ch R = 1,20543,443,443,443
BEGIN DESCRIPTION:
Stream0146 35.0
END DESCRIPTION:
XS GIS Cut Line= 3
      1787275.01     13906124.99      1787675.00     13905725.00
      1788024.97     13905425.03
#Sta/Elev= 30
  4429.3 2255.85  4446.3 2255.61  4473.1 2253.94  4479.7 2253.45  4515.1 2250.59
  4565.1 2249.22  4609.4 2245.68  4729.4 2241.66  4743.4 2239.39  4771.9 2237.00
  4885.2 2233.71  4937.4 2233.11  4958.6 2231.64  4965.8 2230.44  5031.2 2229.38
  5031.5 2228.88  5035.6 2229.38  5046.3 2230.85  5069.3 2232.18  5073.9 2233.20
  5080.8 2232.73  5110.8 2234.37  5129.3 2234.28  5211.3 2238.17  5244.5 2241.70
  5267.6 2242.80  5294.3 2245.25  5377.3 2250.26  5405.0 2253.02  5455.9 2255.42
#Mann=5,-1,0
  4429.3    0.07       0  4473.1     0.1       0  4479.7    0.07       0
  5031.2    0.05       0  5035.6    0.07       0
Bank Sta=5031.2,5035.6
Exp/Cntr=0.3,0.1

Type RM Length L Ch R = 1,20100,422,422,422
BEGIN DESCRIPTION:
Stream0146 34.0
END DESCRIPTION:
XS GIS Cut Line= 3
      1787724.99     13906275.01      1788025.00     13905975.00
      1788174.99     13905825.01
#Sta/Elev= 30
  4575.7 2238.76  4619.9 2237.53  4643.8 2236.45  4656.6 2235.34  4677.8 2234.63
  4699.0 2234.43  4737.2 2233.23  4764.1 2233.22  4788.1 2232.34  4822.1 2232.09
  4827.8 2231.19  4840.5 2231.53  4885.7 2230.57  4957.9 2226.49  4979.1 2224.41
  4991.8 2224.34  5002.4 2223.32  5002.7 2222.82  5006.5 2222.82  5006.8 2223.32
  5013.1 2223.38  5034.3 2225.72  5044.2 2227.36  5059.8 2231.41  5080.9 2232.99
  5090.9 2233.77  5114.9 2234.46  5132.6 2235.83  5141.8 2237.06  5212.1 2240.82
#Mann=4,-1,0
  4575.7    0.07       0  5002.4    0.05       0  5006.8    0.07       0
  5080.9     0.1       0
Bank Sta=5002.4,5006.8
Exp/Cntr=0.3,0.1

Type RM Length L Ch R = 1,19678,444,444,444
BEGIN DESCRIPTION:
Stream0146 33.0
END DESCRIPTION:
XS GIS Cut Line= 3
      1787825.03     13906474.99      1788225.00     13906325.00
      1788424.99     13906075.02
#Sta/Elev= 30
  4567.5 2237.89  4576.2 2237.18  4592.6 2237.34  4643.6 2234.03  4675.5 2232.83
  4681.1 2233.44  4685.1 2232.84  4713.1 2232.04  4723.6 2232.38  4750.4 2230.68
  4839.0 2228.50  4869.7 2226.67  4922.3 2224.09  4952.4 2223.86  4964.0 2222.52
  5004.1 2220.24  5004.4 2219.74  5008.3 2219.74  5008.6 2220.24  5013.4 2220.45
  5035.1 2221.87  5048.7 2223.80  5087.1 2226.78  5102.4 2228.81  5151.7 2231.32
  5190.8 2233.65  5254.0 2236.05  5294.7 2239.21  5309.5 2239.25  5314.8 2239.91
#Mann=7,-1,0
  4567.5     0.1       0  4643.6    0.07       0  4869.7     0.1       0
  5004.1    0.05       0  5008.6     0.1       0  5013.4    0.07       0
  5151.7     0.1       0
Bank Sta=5004.1,5008.6
Exp/Cntr=0.3,0.1

Type RM Length L Ch R = 1,19234,410,410,410
BEGIN DESCRIPTION:
Stream0146 32.0
END DESCRIPTION:
XS GIS Cut Line= 3
      1788174.98     13906825.01      1788475.00     13906675.00
      1788525.00     13906424.99
#Sta/Elev= 30
  4668.9 2229.32  4739.6 2227.81  4760.7 2226.78  4803.4 2226.39  4830.2 2224.71
  4840.3 2224.72  4857.1 2223.34  4873.8 2222.97  4923.3 2220.43  4940.9 2218.45
  4957.7 2217.41  4974.5 2214.75  4986.5 2214.07  4986.8 2213.57  4990.7 2213.57
  4991.0 2214.07  5002.2 2216.25  5037.0 2219.85  5130.7 2225.39  5138.0 2225.70
  5141.1 2225.20  5150.2 2226.51  5177.8 2227.91  5187.0 2227.86  5193.1 2229.10
  5208.4 2228.66  5223.7 2229.84  5235.9 2230.04  5242.0 2229.48  5259.3 2230.09
#Mann=4,-1,0
  4668.9    0.07       0  4986.5    0.05       0  4991.0    0.07       0
  5130.7     0.1       0
Bank Sta=4986.5,4991
Exp/Cntr=0.3,0.1

Type RM Length L Ch R = 1,18824,620,620,620
BEGIN DESCRIPTION:
Stream0146 31.0
END DESCRIPTION:
XS GIS Cut Line= 3
      1788475.02     13907075.00      1788675.00     13907025.00
      1788774.99     13906625.05
#Sta/Elev= 30
  4782.3 2224.66  4816.6 2224.27  4866.1 2220.35  4895.6 2219.01  4909.4 2218.25
  4928.0 2218.23  4955.8 2216.62  4980.4 2211.59  4985.3 2210.26  4999.4 2208.69
  4999.8 2208.19  5003.7 2208.19  5004.0 2208.69  5018.7 2210.30  5031.1 2213.11
  5035.8 2213.79  5091.4 2217.28  5147.1 2218.55  5212.1 2221.10  5215.5 2220.83
  5227.5 2221.46  5270.8 2222.45  5293.0 2221.90  5320.3 2223.61  5323.4 2222.95
  5334.3 2223.59  5348.2 2223.43  5354.4 2223.79  5366.7 2223.40  5400.7 2224.54
#Mann=4,-1,0
  4782.3    0.07       0  4895.6     0.1       0  4999.4    0.05       0
  5004.0     0.1       0
Bank Sta=4999.4,5004
Exp/Cntr=0.3,0.1

Type RM Length L Ch R = 1,18204,295,295,295
BEGIN DESCRIPTION:
Stream0146 30.0
END DESCRIPTION:
XS GIS Cut Line= 3
      1788725.05     13907475.00      1789039.13     13907483.51
      1789775.04     13907224.99
#Sta/Elev= 30
  4689.9 2225.41  4696.5 2225.27  4755.2 2223.00  4764.4 2221.57  4785.2 2220.83
  4809.2 2218.67  4863.3 2217.04  4866.7 2215.98  4905.3 2213.04  4929.3 2210.21
  4938.3 2208.23  4962.3 2208.53  4974.3 2206.14  4983.1 2205.86  4983.6 2205.36
  4990.1 2205.86  5018.6 2206.56  5029.8 2208.62  5048.3 2210.58  5077.5 2212.21
  5157.5 2214.92  5214.8 2215.98  5310.5 2216.88  5328.8 2218.03  5386.1 2219.39
  5504.4 2224.31  5583.3 2228.78  5656.6 2231.27  5774.6 2236.52  5784.1 2237.36
#Mann=7,-1,0
  4689.9    0.07       0  4696.5     0.1       0  4983.1    0.05       0
  4990.1     0.1       0  5214.8    0.07       0  5656.6     0.1       0
  5774.6    0.07       0
Bank Sta=4983.1,4990.1
Exp/Cntr=0.3,0.1

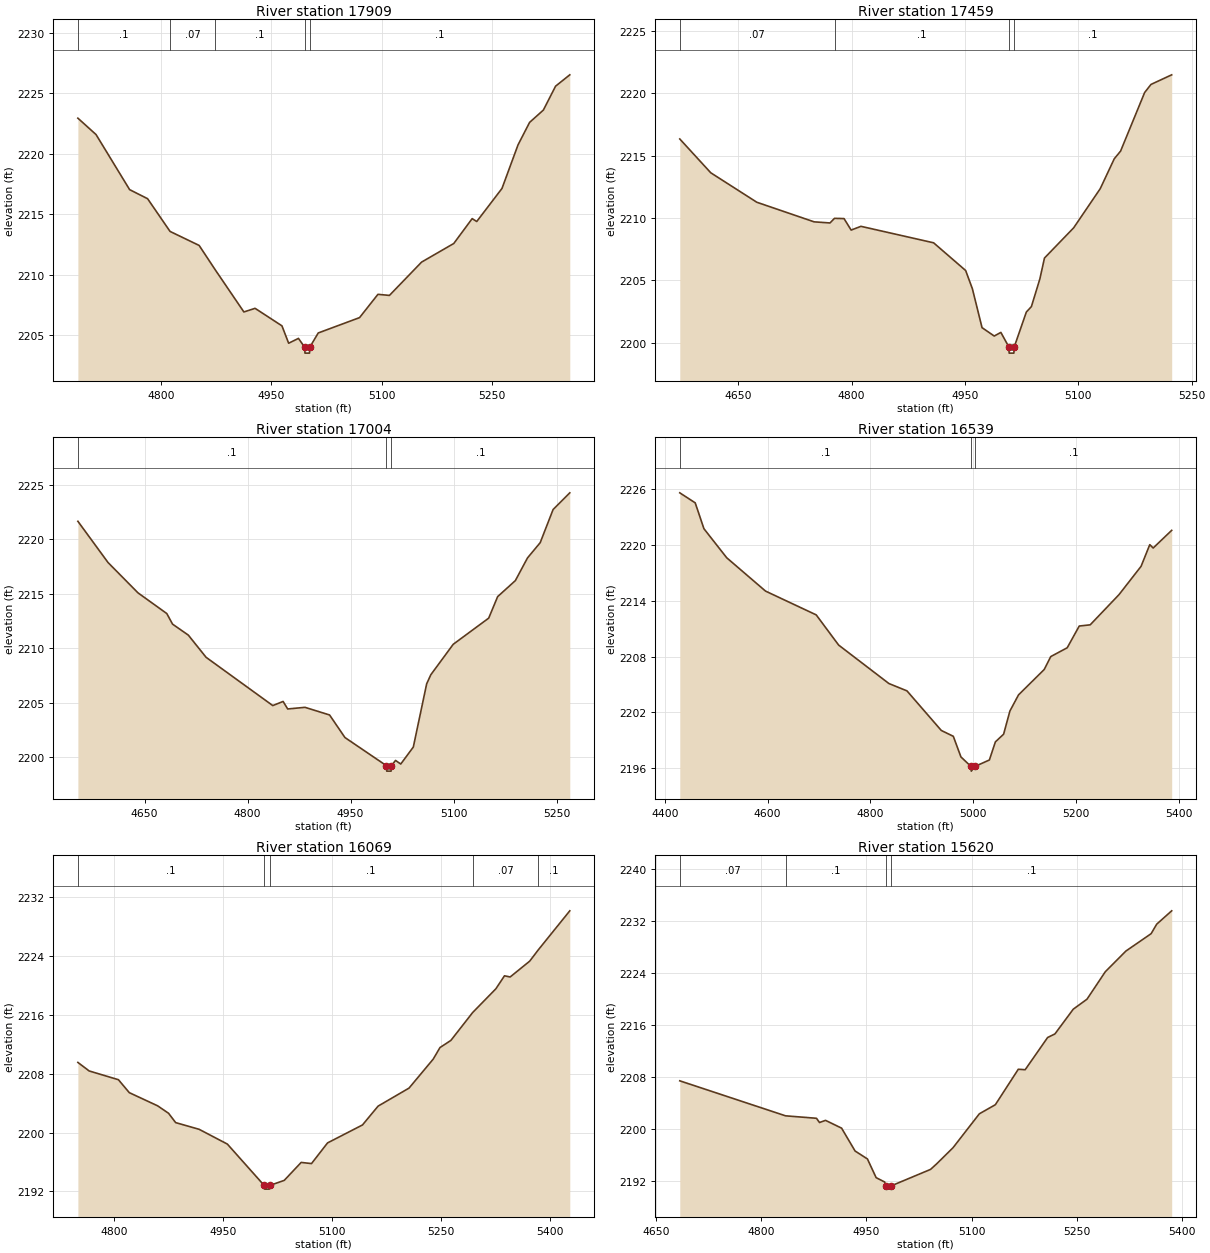
Type RM Length L Ch R = 1,17909,450,450,450
BEGIN DESCRIPTION:
Stream0146 29.0
END DESCRIPTION:
XS GIS Cut Line= 3
      1788924.99     13907625.00      1789225.00     13907675.00
      1789575.04     13907574.99
#Sta/Elev= 30
  4687.5 2222.95  4712.2 2221.59  4757.8 2217.03  4782.2 2216.28  4812.7 2213.57
  4852.2 2212.41  4874.1 2210.39  4913.0 2206.90  4928.2 2207.20  4964.7 2205.75
  4973.8 2204.31  4987.1 2204.71  4995.5 2203.99  4996.0 2203.49  5002.1 2203.49
  5002.6 2203.99  5014.0 2205.16  5070.1 2206.43  5095.1 2208.36  5110.7 2208.27
  5154.4 2211.03  5198.1 2212.57  5223.1 2214.63  5229.3 2214.39  5263.6 2217.13
  5285.4 2220.74  5301.1 2222.60  5319.8 2223.62  5336.4 2225.60  5355.7 2226.54
#Mann=5,-1,0
  4687.5     0.1       0  4812.7    0.07       0  4874.1     0.1       0
  4995.5    0.05       0  5002.6     0.1       0
Bank Sta=4995.5,5002.6
Exp/Cntr=0.3,0.1

Type RM Length L Ch R = 1,17459,455,455,455
BEGIN DESCRIPTION:
Stream0146 28.0
END DESCRIPTION:
XS GIS Cut Line= 3
      1789024.98     13907874.99      1789425.00     13908025.00
      1789624.98     13908124.99
#Sta/Elev= 30
  4572.7 2216.34  4613.7 2213.63  4674.6 2211.27  4750.4 2209.70  4771.4 2209.61
  4777.4 2209.98  4790.0 2209.96  4799.4 2209.04  4812.4 2209.34  4908.5 2208.02
  4950.9 2205.80  4959.8 2204.34  4972.6 2201.22  4988.7 2200.55  4997.5 2200.84
  5008.0 2199.68  5008.5 2199.18  5014.7 2199.18  5015.2 2199.68  5031.2 2202.47
  5037.9 2202.91  5049.1 2205.13  5055.2 2206.80  5093.8 2209.22  5129.0 2212.36
  5147.5 2214.75  5155.9 2215.37  5187.7 2220.06  5196.1 2220.71  5223.5 2221.48
#Mann=4,-1,0
  4572.7    0.07       0  4777.4     0.1       0  5008.0    0.05       0
  5015.2     0.1       0
Bank Sta=5008,5015.2
Exp/Cntr=0.3,0.1

Type RM Length L Ch R = 1,17004,465,465,465
BEGIN DESCRIPTION:
Stream0146 27.0
END DESCRIPTION:
XS GIS Cut Line= 3
      1788925.01     13908225.01      1789325.00     13908425.00
      1789575.04     13908525.02
#Sta/Elev= 30
  4552.8 2221.66  4596.7 2217.88  4640.3 2215.10  4682.3 2213.20  4690.7 2212.23
  4713.7 2211.22  4739.5 2209.19  4836.7 2204.76  4851.7 2205.14  4858.4 2204.45
  4883.6 2204.60  4919.4 2203.90  4941.8 2201.83  5002.2 2199.25  5002.7 2198.75
  5009.0 2198.75  5009.5 2199.25  5015.5 2199.73  5023.1 2199.40  5041.4 2200.96
  5060.8 2206.75  5066.9 2207.59  5099.5 2210.38  5151.2 2212.78  5164.2 2214.75
  5190.0 2216.22  5207.7 2218.30  5226.2 2219.70  5245.0 2222.74  5269.3 2224.27
#Mann=3,-1,0
  4552.8     0.1       0  5002.2    0.05       0  5009.5     0.1       0
Bank Sta=5002.2,5009.5
Exp/Cntr=0.3,0.1

Type RM Length L Ch R = 1,16539,470,470,470
BEGIN DESCRIPTION:
Stream0146 26.0
END DESCRIPTION:
XS GIS Cut Line= 3
      1788625.01     13908325.01      1789025.00     13908725.00
      1789325.01     13908975.01
#Sta/Elev= 30
  4429.3 2225.64  4459.3 2224.56  4476.2 2221.78  4520.5 2218.65  4596.0 2215.06
  4694.5 2212.50  4738.1 2209.25  4835.8 2205.11  4870.9 2204.32  4937.6 2200.06
  4961.0 2199.43  4975.8 2197.21  4995.4 2196.18  4995.9 2195.68  5002.9 2196.18
  5031.1 2196.88  5042.8 2198.83  5058.8 2199.66  5071.0 2202.15  5087.8 2203.89
  5137.7 2206.62  5150.4 2208.01  5182.4 2208.96  5205.8 2211.30  5227.1 2211.43
  5283.1 2214.68  5326.0 2217.73  5342.9 2220.06  5349.5 2219.70  5385.5 2221.60
#Mann=3,-1,0
  4429.3     0.1       0  4995.4    0.05       0  5002.9     0.1       0
Bank Sta=4995.4,5002.9
Exp/Cntr=0.3,0.1

Type RM Length L Ch R = 1,16069,449,449,449
BEGIN DESCRIPTION:
Stream0146 25.0
END DESCRIPTION:
XS GIS Cut Line= 3
      1788524.99     13908824.99      1788675.00     13909025.00
      1788824.99     13909424.98
#Sta/Elev= 30
  4750.0 2209.54  4765.5 2208.38  4805.8 2207.19  4820.8 2205.43  4859.8 2203.64
  4874.8 2202.63  4884.6 2201.36  4916.9 2200.45  4955.8 2198.44  5006.5 2192.82
  5007.0 2192.32  5013.7 2192.32  5014.2 2192.82  5034.1 2193.51  5057.4 2195.95
  5071.6 2195.79  5093.7 2198.60  5141.8 2201.04  5163.3 2203.60  5205.9 2206.05
  5239.2 2209.99  5248.5 2211.56  5263.5 2212.53  5293.5 2216.32  5325.4 2219.54
  5337.3 2221.31  5345.1 2221.15  5372.0 2223.30  5383.8 2224.83  5427.2 2230.14
#Mann=5,-1,0
  4750.0     0.1       0  5006.5    0.05       0  5014.2     0.1       0
  5293.5    0.07       0  5383.8     0.1       0
Bank Sta=5006.5,5014.2
Exp/Cntr=0.3,0.1

Type RM Length L Ch R = 1,15620,469,469,469
BEGIN DESCRIPTION:
Stream0146 24.0
END DESCRIPTION:
XS GIS Cut Line= 3
      1788174.97     13909174.97      1788425.00     13909375.00
      1788775.01     13909525.01
#Sta/Elev= 30
  4684.2 2207.42  4834.9 2202.03  4879.0 2201.65  4883.3 2201.00  4891.9 2201.33
  4914.8 2200.13  4934.0 2196.61  4951.6 2195.39  4964.0 2192.51  4976.3 2191.83
  4977.6 2191.24  4978.1 2190.74  4984.9 2190.74  4985.4 2191.24  5041.6 2193.78
  5050.7 2194.68  5073.6 2197.12  5111.1 2202.34  5133.9 2203.74  5166.6 2209.20
  5176.4 2209.13  5208.4 2214.09  5218.8 2214.64  5244.9 2218.45  5264.5 2219.99
  5290.6 2224.22  5320.0 2227.41  5355.9 2230.08  5363.8 2231.54  5385.2 2233.60
#Mann=4,-1,0
  4684.2    0.07       0  4834.9     0.1       0  4977.6    0.05       0
  4985.4     0.1       0
Bank Sta=4977.6,4985.4
Exp/Cntr=0.3,0.1

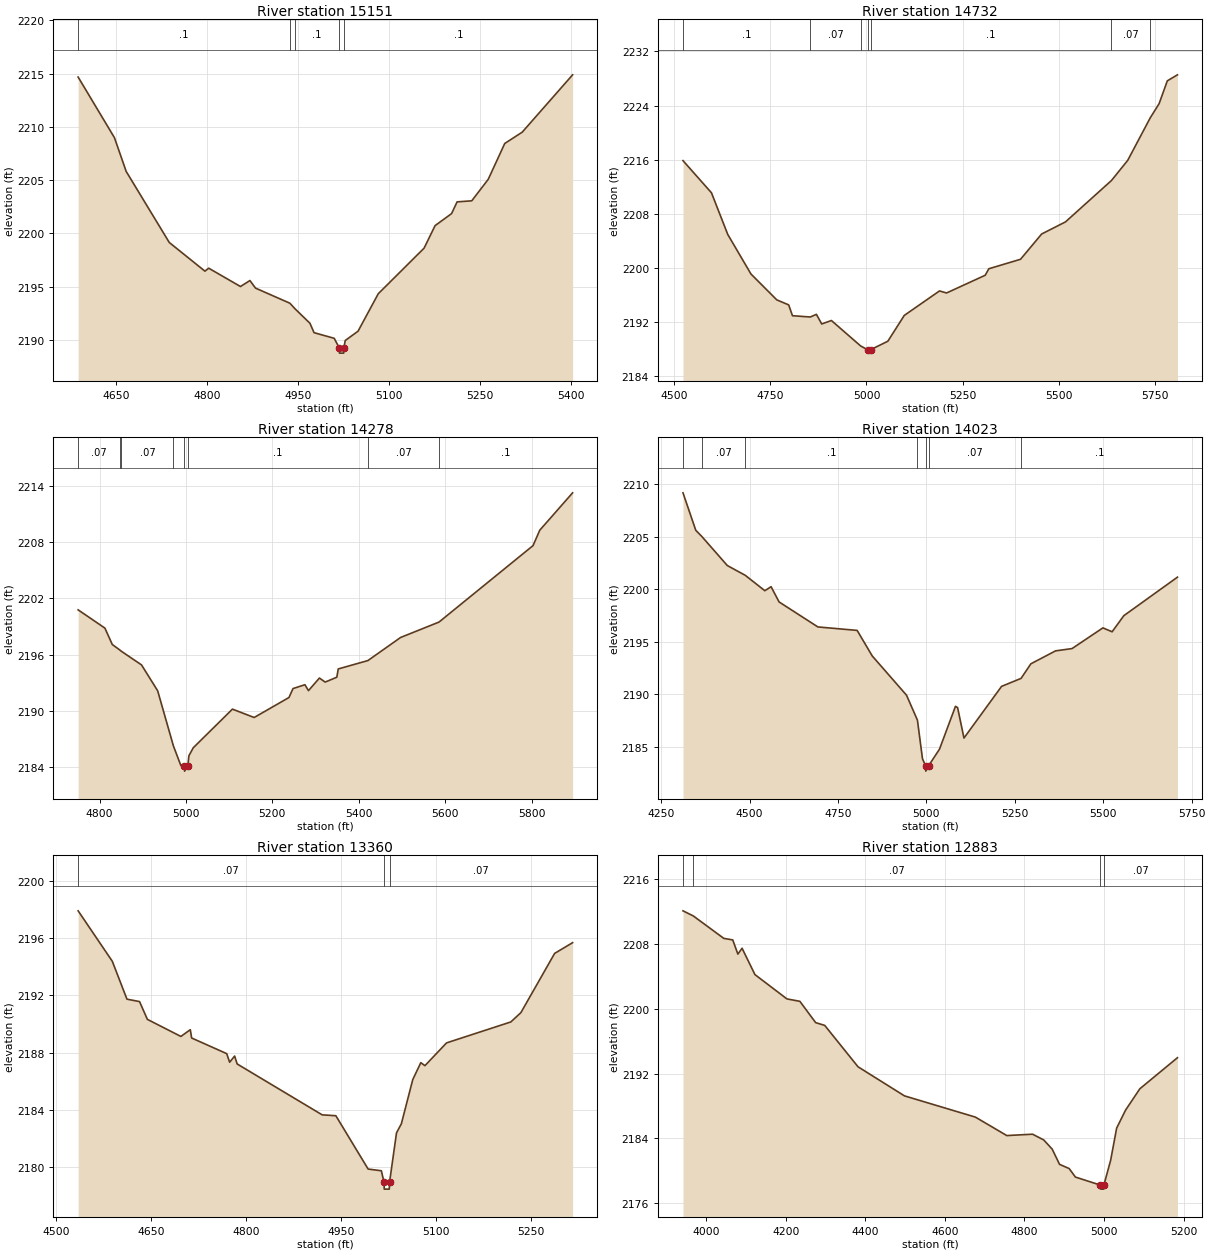
Type RM Length L Ch R = 1,15151,419,419,419
BEGIN DESCRIPTION:
Stream0146 23.0
END DESCRIPTION:
XS GIS Cut Line= 3
      1787825.03     13909675.01      1788225.00     13909775.00
      1788625.01     13909725.00
#Sta/Elev= 30
  4587.7 2214.67  4647.6 2208.98  4666.9 2205.82  4738.0 2199.15  4796.8 2196.46
  4803.0 2196.74  4855.4 2195.02  4871.0 2195.58  4880.2 2194.87  4937.0 2193.45
  4944.8 2192.96  4970.0 2191.57  4976.7 2190.69  5010.0 2190.16  5018.2 2189.27
  5018.7 2188.77  5025.5 2188.77  5026.0 2189.27  5028.1 2189.95  5049.3 2190.83
  5082.6 2194.34  5158.2 2198.62  5176.3 2200.73  5203.5 2201.86  5212.6 2202.96
  5236.8 2203.06  5264.0 2205.08  5291.2 2208.44  5320.0 2209.50  5403.1 2214.88
#Mann=5,-1,0
  4587.7     0.1       0  4937.0    0.07       0  4944.8     0.1       0
  5018.2    0.05       0  5026.0     0.1       0
Bank Sta=5018.2,5026
Exp/Cntr=0.3,0.1

Type RM Length L Ch R = 1,14732,454,454,454
BEGIN DESCRIPTION:
Stream0146 22.0
END DESCRIPTION:
XS GIS Cut Line= 3
      1787775.00     13909725.01      1788025.00     13910125.00
      1788824.97     13909975.01
#Sta/Elev= 30
  4523.0 2215.87  4597.1 2211.11  4639.5 2204.95  4699.8 2199.11  4766.9 2195.29
  4797.8 2194.55  4807.6 2192.95  4854.0 2192.76  4869.9 2193.15  4883.7 2191.73
  4908.9 2192.24  4984.9 2188.48  5002.8 2187.92  5003.3 2187.42  5010.7 2187.92
  5055.6 2189.18  5098.3 2192.99  5189.9 2196.61  5208.3 2196.31  5308.8 2198.93
  5318.2 2199.89  5400.6 2201.29  5455.6 2205.03  5517.4 2206.81  5637.0 2212.93
  5679.3 2215.91  5737.9 2222.20  5760.9 2224.29  5782.2 2227.66  5808.6 2228.55
#Mann=7,-1,0
  4523.0     0.1       0  4854.0    0.07       0  4984.9     0.1       0
  5002.8    0.05       0  5010.7     0.1       0  5637.0    0.07       0
  5737.9     0.1       0
Bank Sta=5002.8,5010.7
Exp/Cntr=0.3,0.1

Type RM Length L Ch R = 1,14278,255,255,255
BEGIN DESCRIPTION:
Stream0146 21.0
END DESCRIPTION:
XS GIS Cut Line= 3
      1787674.99     13910374.99      1787875.00     13910525.00
      1788674.97     13910125.02
#Sta/Elev= 30
  4750.5 2200.76  4812.4 2198.82  4829.6 2197.07  4846.6 2196.50  4850.6 2196.35
  4897.2 2194.90  4934.6 2192.14  4970.9 2186.29  4988.2 2184.19  4996.3 2184.09
  4996.8 2183.59  5004.2 2184.09  5006.9 2185.23  5017.0 2186.08  5107.6 2190.19
  5157.9 2189.30  5238.5 2191.43  5247.8 2192.38  5275.4 2192.79  5283.6 2192.16
  5308.9 2193.50  5322.3 2193.07  5349.2 2193.59  5352.5 2194.47  5421.1 2195.36
  5496.8 2197.82  5585.7 2199.46  5803.3 2207.60  5818.9 2209.24  5894.9 2213.22
#Mann=8,-1,0
  4750.5    0.07       0  4846.6     0.1       0  4850.6    0.07       0
  4970.9     0.1       0  4996.3    0.05       0  5004.2     0.1       0
  5421.1    0.07       0  5585.7     0.1       0
Bank Sta=4996.3,5004.2
Exp/Cntr=0.3,0.1

Type RM Length L Ch R = 1,14023,663,663,663
BEGIN DESCRIPTION:
Stream0146 20.1
END DESCRIPTION:
XS GIS Cut Line= 4
      1787411.46     13910352.97      1787825.34     13910771.28
      1788107.20     13910751.11      1788615.13     13910610.75
#Sta/Elev= 30
  4311.9 2209.16  4348.1 2205.59  4365.3 2205.00  4437.1 2202.24  4488.2 2201.30
  4543.3 2199.84  4561.0 2200.22  4583.6 2198.77  4693.3 2196.39  4804.3 2196.06
  4846.9 2193.63  4943.9 2189.89  4974.8 2187.51  4989.0 2183.84  4997.8 2183.16
  4998.3 2182.66  5006.1 2183.16  5037.1 2184.75  5082.3 2188.83  5088.3 2188.71
  5106.3 2185.81  5212.6 2190.73  5267.7 2191.49  5295.5 2192.88  5365.2 2194.11
  5411.9 2194.33  5499.1 2196.30  5525.2 2195.93  5558.2 2197.46  5709.9 2201.13
#Mann=7,-1,0
  4311.9     0.1       0  4365.3    0.07       0  4488.2     0.1       0
  4974.8    0.07       0  4997.8    0.05       0  5006.1    0.07       0
  5267.7     0.1       0
Bank Sta=4997.8,5006.1
Exp/Cntr=0.3,0.1

Type RM Length L Ch R = 1,13360,477,477,477
BEGIN DESCRIPTION:
Stream0146 20.0
END DESCRIPTION:
XS GIS Cut Line= 3
      1787675.00     13911025.00      1788025.00     13911325.00
      1788274.98     13911524.98
#Sta/Elev= 30
  4534.6 2197.89  4588.6 2194.37  4611.7 2191.73  4631.6 2191.56  4644.0 2190.32
  4696.9 2189.13  4711.8 2189.60  4713.9 2189.02  4769.3 2187.93  4773.9 2187.33
  4781.8 2187.76  4785.8 2187.21  4920.1 2183.66  4941.7 2183.60  4992.7 2179.88
  5013.6 2179.76  5017.7 2178.98  5018.2 2178.48  5026.1 2178.48  5026.6 2178.98
  5037.5 2182.40  5045.2 2183.04  5063.2 2186.12  5075.9 2187.30  5082.4 2187.09
  5116.6 2188.68  5218.1 2190.14  5234.0 2190.79  5287.3 2194.92  5315.7 2195.67
#Mann=3,-1,0
  4534.6    0.07       0  5017.7    0.05       0  5026.6    0.07       0
Bank Sta=5017.7,5026.6
Exp/Cntr=0.3,0.1

Type RM Length L Ch R = 1,12883,445,445,445
BEGIN DESCRIPTION:
Stream0146 19.0
END DESCRIPTION:
XS GIS Cut Line= 3
      1787225.00     13910974.99      1787925.00     13911775.00
      1788075.00     13911875.00
#Sta/Elev= 30
  3941.5 2212.09  3967.4 2211.46  4044.1 2208.69  4066.6 2208.50  4079.5 2206.75
  4090.1 2207.47  4122.4 2204.22  4202.8 2201.22  4235.4 2200.92  4275.1 2198.29
  4297.9 2197.95  4381.6 2192.84  4498.4 2189.25  4676.7 2186.63  4755.7 2184.35
  4820.5 2184.52  4848.6 2183.81  4869.8 2182.68  4888.3 2180.80  4912.5 2180.28
  4928.2 2179.23  4990.8 2178.24  4991.3 2177.74  4999.3 2177.74  4999.8 2178.24
  5016.8 2181.30  5031.9 2185.27  5054.3 2187.49  5090.3 2190.13  5184.8 2193.96
#Mann=4,-1,0
  3941.5     0.1       0  3967.4    0.07       0  4990.8    0.05       0
  4999.8    0.07       0
Bank Sta=4990.8,4999.8
Exp/Cntr=0.3,0.1

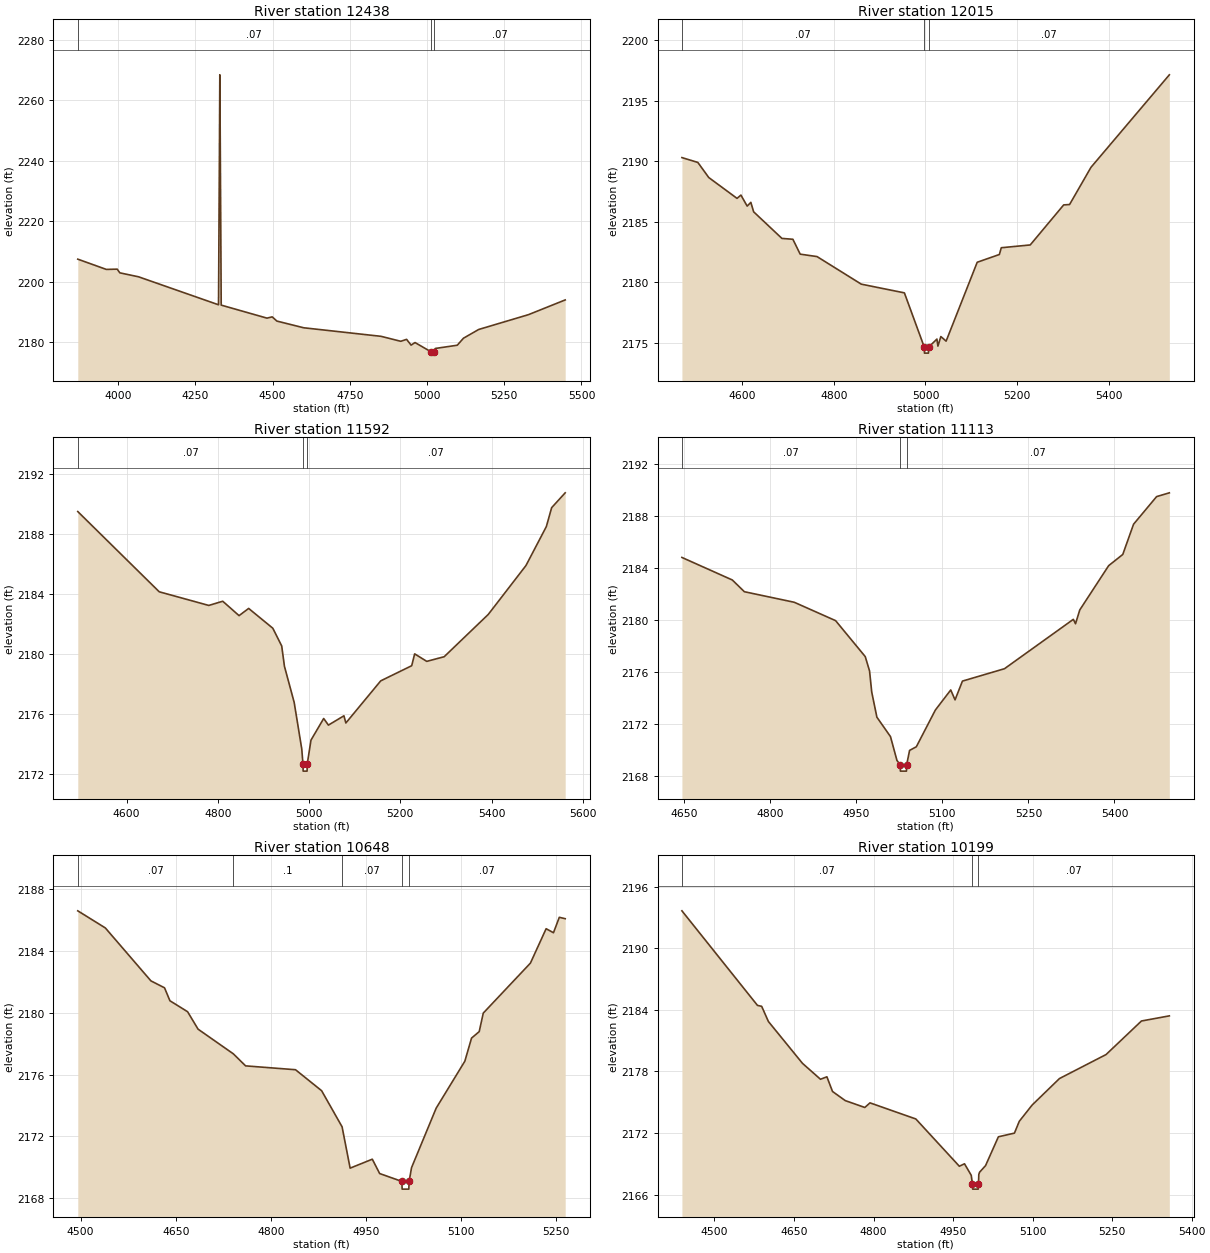
Type RM Length L Ch R = 1,12438,423,423,423
BEGIN DESCRIPTION:
Stream0146 18.0
END DESCRIPTION:
XS GIS Cut Line= 3
      1786824.98     13911274.98      1787625.00     13912075.00
      1787824.99     13912474.98
#Sta/Elev= 30
  3868.8 2207.52  3961.3 2204.13  3996.5 2204.22  4005.0 2203.00  4065.7 2201.69
  4324.6 2192.45  4325.4 2205.21  4326.2 2220.60  4327.5 2242.32  4328.8 2268.41
  4330.0 2250.06  4333.3 2192.34  4481.5 2188.04  4498.5 2188.46  4513.5 2187.07
  4600.7 2184.85  4850.9 2182.03  4914.8 2180.39  4933.7 2181.03  4948.3 2179.13
  4961.1 2179.97  5011.8 2176.98  5012.3 2176.48  5021.3 2176.98  5026.6 2178.02
  5097.8 2179.09  5118.0 2181.41  5167.2 2184.29  5328.2 2189.18  5447.4 2194.05
#Mann=3,-1,0
  3868.8    0.07       0  5011.8    0.05       0  5021.3    0.07       0
Bank Sta=5011.8,5021.3
Exp/Cntr=0.3,0.1

Type RM Length L Ch R = 1,12015,423,423,423
BEGIN DESCRIPTION:
Stream0146 17.0
END DESCRIPTION:
XS GIS Cut Line= 3
      1786875.04     13911925.03      1787275.00     13912275.00
      1787625.02     13912675.02
#Sta/Elev= 30
  4468.8 2190.31  4503.5 2189.91  4527.4 2188.66  4589.0 2186.94  4597.5 2187.21
  4611.1 2186.30  4619.1 2186.61  4625.2 2185.83  4686.9 2183.63  4710.8 2183.56
  4726.7 2182.33  4763.4 2182.13  4860.0 2179.85  4954.0 2179.13  4997.3 2174.65
  4997.8 2174.15  5006.4 2174.15  5006.9 2174.65  5024.9 2175.31  5027.1 2174.73
  5033.5 2175.52  5045.0 2175.14  5112.8 2181.66  5161.1 2182.30  5165.3 2182.86
  5228.4 2183.09  5301.4 2186.40  5314.2 2186.43  5361.0 2189.51  5531.8 2197.15
#Mann=3,-1,0
  4468.8    0.07       0  4997.3    0.05       0  5006.9    0.07       0
Bank Sta=4997.3,5006.9
Exp/Cntr=0.3,0.1

Type RM Length L Ch R = 1,11592,479,479,479
BEGIN DESCRIPTION:
Stream0146 16.0
END DESCRIPTION:
XS GIS Cut Line= 3
      1786875.00     13911974.95      1786925.00     13912475.00
      1787324.98     13912874.98
#Sta/Elev= 30
  4493.1 2189.52  4671.6 2184.17  4780.2 2183.26  4810.8 2183.54  4846.5 2182.58
  4867.6 2183.06  4920.5 2181.74  4940.0 2180.56  4946.0 2179.20  4967.3 2176.80
  4984.0 2173.68  4986.5 2172.71  4987.0 2172.21  4995.6 2172.21  4996.1 2172.71
  5004.2 2174.28  5032.0 2175.72  5042.4 2175.28  5076.4 2175.90  5080.6 2175.42
  5157.0 2178.23  5224.9 2179.24  5231.4 2180.03  5257.9 2179.53  5296.1 2179.84
  5392.7 2182.66  5475.3 2185.92  5520.0 2188.52  5531.6 2189.78  5561.3 2190.77
#Mann=3,-1,0
  4493.1    0.07       0  4986.5    0.05       0  4996.1    0.07       0
Bank Sta=4986.5,4996.1
Exp/Cntr=0.3,0.1

Type RM Length L Ch R = 1,11113,465,465,465
BEGIN DESCRIPTION:
Stream0146 15.0
END DESCRIPTION:
XS GIS Cut Line= 3
      1786374.98     13912875.00      1786725.00     13912875.00
      1787124.99     13913174.99
#Sta/Elev= 30
  4645.7 2184.80  4733.6 2183.07  4754.6 2182.17  4841.6 2181.36  4913.7 2179.95
  4965.4 2177.19  4972.9 2176.09  4976.7 2174.47  4985.7 2172.54  5009.4 2171.05
  5020.7 2169.22  5026.2 2168.90  5026.7 2168.40  5037.2 2168.40  5037.7 2168.90
  5042.7 2169.99  5054.5 2170.27  5087.7 2173.09  5114.5 2174.63  5122.0 2173.87
  5134.9 2175.31  5208.2 2176.26  5328.3 2180.05  5332.1 2179.71  5339.5 2180.77
  5389.9 2184.17  5414.5 2185.03  5433.3 2187.35  5473.5 2189.47  5495.7 2189.76
#Mann=3,-1,0
  4645.7    0.07       0  5026.2    0.05       0  5037.7    0.07       0
Bank Sta=5026.2,5037.7
Exp/Cntr=0.3,0.1

Type RM Length L Ch R = 1,10648,449,449,449
BEGIN DESCRIPTION:
Stream0146 14.0
END DESCRIPTION:
XS GIS Cut Line= 3
      1786275.03     13913025.02      1786675.00     13913325.00
      1786924.98     13913424.99
#Sta/Elev= 30
  4495.5 2186.61  4539.0 2185.50  4610.9 2182.07  4632.4 2181.62  4640.9 2180.78
  4668.8 2180.07  4685.3 2178.94  4741.0 2177.34  4760.3 2176.56  4839.1 2176.31
  4880.3 2174.95  4912.6 2172.61  4925.3 2169.93  4960.3 2170.51  4971.9 2169.58
  5006.9 2169.07  5007.4 2168.57  5017.9 2168.57  5018.4 2169.07  5022.2 2169.96
  5061.1 2173.82  5106.3 2176.86  5116.9 2178.36  5129.0 2178.78  5135.4 2179.98
  5209.8 2183.22  5234.6 2185.45  5246.2 2185.19  5255.4 2186.19  5264.7 2186.10
#Mann=5,-1,0
  4495.5    0.07       0  4741.0     0.1       0  4912.6    0.07       0
  5006.9    0.05       0  5018.4    0.07       0
Bank Sta=5006.9,5018.4
Exp/Cntr=0.3,0.1

Type RM Length L Ch R = 1,10199,452,452,452
BEGIN DESCRIPTION:
Stream0146 13.0
END DESCRIPTION:
XS GIS Cut Line= 3
      1786125.01     13913325.01      1786525.00     13913725.00
      1786874.98     13913675.00
#Sta/Elev= 30
  4438.7 2193.66  4581.2 2184.44  4589.1 2184.35  4601.8 2182.87  4666.1 2178.79
  4700.0 2177.24  4712.1 2177.48  4722.7 2176.05  4746.7 2175.16  4783.6 2174.49
  4793.4 2174.94  4879.8 2173.37  4961.9 2168.76  4971.6 2169.00  4984.3 2167.88
  4986.5 2167.03  4987.0 2166.53  4997.5 2166.53  4998.0 2167.03  4998.6 2167.96
  5000.1 2168.18  5011.3 2168.82  5035.5 2171.63  5065.8 2171.99  5074.9 2173.14
  5099.2 2174.73  5150.7 2177.31  5238.6 2179.65  5305.3 2182.92  5357.9 2183.42
#Mann=3,-1,0
  4438.7    0.07       0  4986.5    0.05       0  4998.0    0.07       0
Bank Sta=4986.5,4998
Exp/Cntr=0.3,0.1

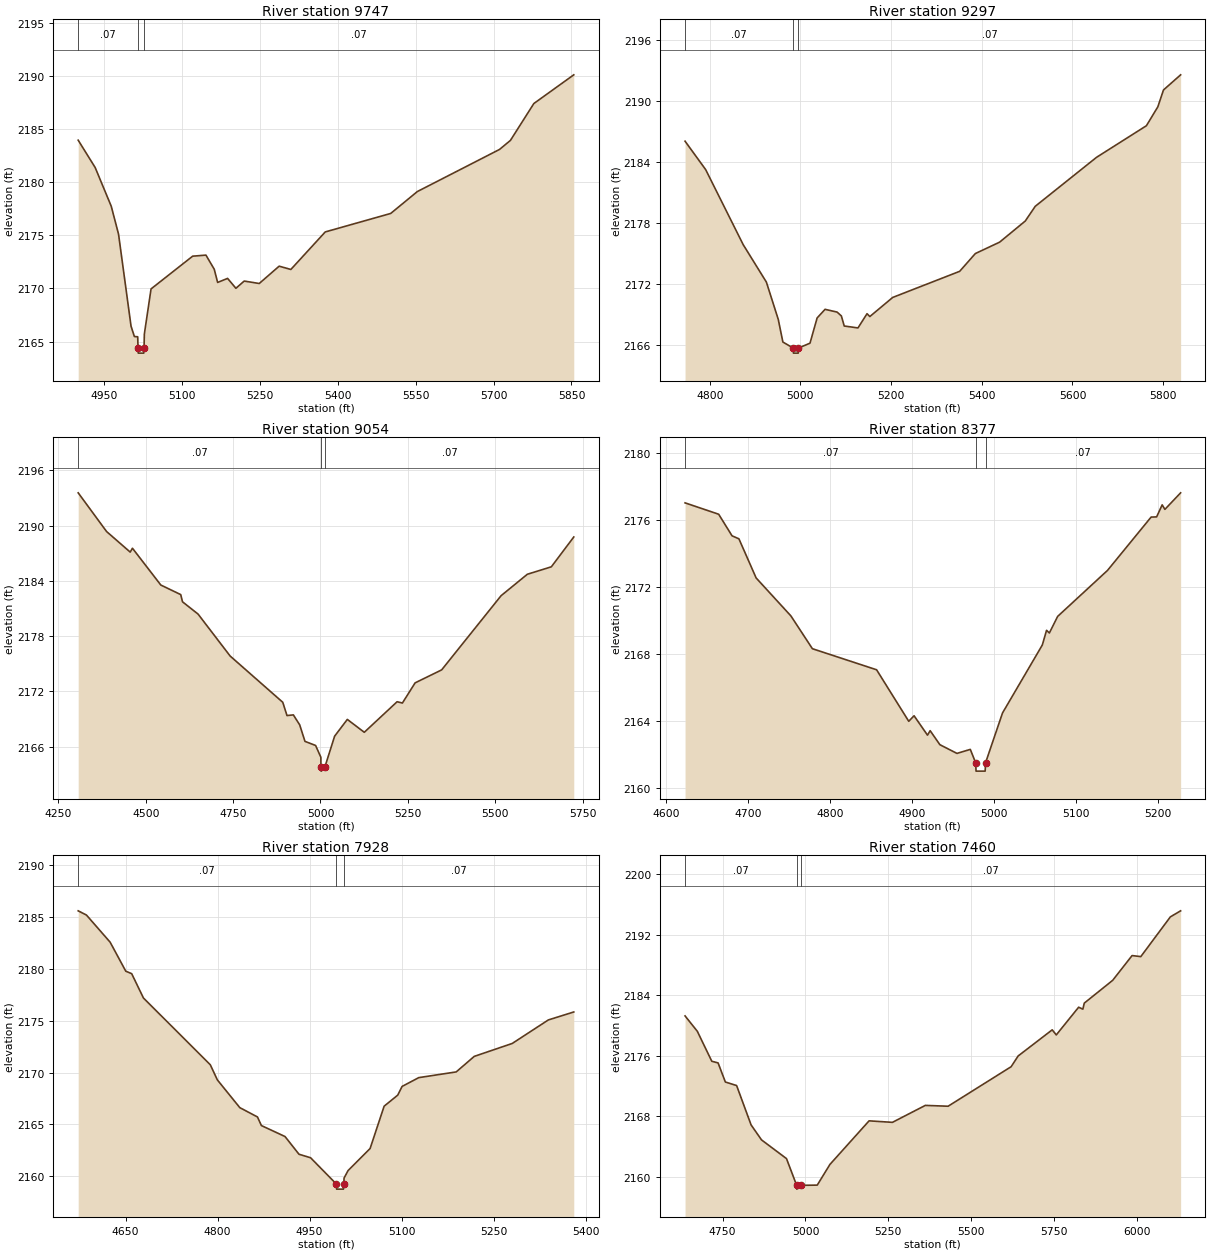
Type RM Length L Ch R = 1,9747,450,450,450
BEGIN DESCRIPTION:
Stream0146 12.0
END DESCRIPTION:
XS GIS Cut Line= 3
      1786175.04     13914075.00      1786275.00     13914075.00
      1787074.95     13913775.02
#Sta/Elev= 30
  4900.2 2183.94  4932.9 2181.37  4963.9 2177.72  4977.9 2175.10  5002.0 2166.44
  5008.4 2165.47  5014.8 2165.45  5015.4 2164.41  5015.9 2163.91  5026.5 2163.91
  5027.0 2164.41  5027.6 2165.71  5040.5 2169.95  5120.6 2173.03  5146.2 2173.13
  5162.2 2171.80  5168.7 2170.56  5187.9 2170.94  5203.9 2170.01  5219.9 2170.69
  5248.8 2170.46  5287.2 2172.09  5309.7 2171.78  5375.9 2175.31  5502.0 2177.05
  5553.3 2179.11  5711.5 2183.07  5732.5 2183.92  5777.6 2187.39  5854.5 2190.09
#Mann=3,-1,0
  4900.2    0.07       0  5015.4    0.05       0  5027.0    0.07       0
Bank Sta=5015.4,5027
Exp/Cntr=0.3,0.1

Type RM Length L Ch R = 1,9297,243,243,243
BEGIN DESCRIPTION:
Stream0146 11.0
END DESCRIPTION:
XS GIS Cut Line= 3
      1786175.02     13914425.00      1786425.00     13914475.00
      1787225.02     13914224.99
#Sta/Elev= 30
  4745.5 2186.09  4791.0 2183.29  4873.7 2175.91  4924.9 2172.22  4951.1 2168.55
  4961.3 2166.32  4984.1 2165.73  4984.6 2165.23  4995.2 2165.23  4995.7 2165.73
  5021.1 2166.21  5036.8 2168.69  5054.3 2169.54  5080.8 2169.27  5090.3 2168.89
  5096.6 2167.90  5126.9 2167.71  5146.9 2169.11  5153.1 2168.83  5203.5 2170.71
  5351.2 2173.28  5385.8 2175.03  5439.3 2176.15  5495.9 2178.23  5517.9 2179.68
  5653.1 2184.50  5763.1 2187.61  5788.3 2189.47  5800.8 2191.13  5838.6 2192.62
#Mann=3,-1,0
  4745.5    0.07       0  4984.1    0.05       0  4995.7    0.07       0
Bank Sta=4984.1,4995.7
Exp/Cntr=0.3,0.1

Type RM Length L Ch R = 1,9054,677,677,677
BEGIN DESCRIPTION:
Stream0146 10.1
END DESCRIPTION:
XS GIS Cut Line= 4
      1785928.99     13914436.89      1786278.64     13914711.84
      1786825.20     13914636.72      1787211.88     13914469.72
#Sta/Elev= 30
  4306.9 2193.57  4388.2 2189.36  4455.7 2187.13  4462.1 2187.55  4543.3 2183.55
  4600.3 2182.51  4605.3 2181.73  4649.9 2180.39  4741.5 2175.84  4892.1 2170.81
  4904.2 2169.37  4922.4 2169.44  4940.5 2168.36  4955.7 2166.56  4986.0 2166.12
  5001.1 2164.84  5001.3 2163.83  5001.8 2163.33  5013.0 2163.83  5040.5 2167.13
  5076.8 2168.95  5125.3 2167.55  5219.2 2170.87  5234.4 2170.73  5270.7 2172.92
  5346.6 2174.33  5516.6 2182.39  5591.7 2184.72  5660.4 2185.53  5724.6 2188.77
#Mann=3,-1,0
  4306.9    0.07       0  5001.3    0.05       0  5013.0    0.07       0
Bank Sta=5001.3,5013
Exp/Cntr=0.3,0.1

Type RM Length L Ch R = 1,8377,449,449,449
BEGIN DESCRIPTION:
Stream0146 10.0
END DESCRIPTION:
XS GIS Cut Line= 3
      1786575.03     13915324.99      1786925.00     13915175.00
      1787125.03     13915074.99
#Sta/Elev= 30
  4623.3 2177.04  4664.3 2176.36  4680.6 2175.07  4689.0 2174.89  4710.0 2172.55
  4752.4 2170.28  4778.6 2168.32  4856.9 2167.06  4896.1 2163.98  4902.6 2164.31
  4919.0 2163.15  4922.2 2163.42  4934.1 2162.58  4954.9 2162.06  4971.2 2162.30
  4977.7 2161.50  4978.2 2161.00  4989.3 2161.00  4989.8 2161.50  5010.5 2164.48
  5059.0 2168.54  5064.2 2169.42  5067.6 2169.26  5077.7 2170.25  5138.5 2173.00
  5191.7 2176.19  5198.4 2176.20  5205.2 2176.92  5208.5 2176.65  5227.7 2177.64
#Mann=3,-1,0
  4623.3    0.07       0  4977.7    0.05       0  4989.8    0.07       0
Bank Sta=4977.7,4989.8
Exp/Cntr=0.3,0.1

Type RM Length L Ch R = 1,7928,468,468,468
BEGIN DESCRIPTION:
Stream0146 9.0
END DESCRIPTION:
XS GIS Cut Line= 3
      1786525.00     13915775.00      1786925.00     13915625.00
      1787275.01     13915474.99
#Sta/Elev= 30
  4572.8 2185.62  4586.3 2185.21  4624.9 2182.59  4650.4 2179.79  4660.0 2179.55
  4679.2 2177.20  4788.2 2170.75  4799.7 2169.29  4836.3 2166.61  4865.1 2165.71
  4871.5 2164.88  4910.0 2163.82  4932.8 2162.11  4951.7 2161.77  4993.6 2159.24
  4994.1 2158.74  5005.3 2158.74  5005.8 2159.24  5006.3 2159.81  5012.8 2160.53
  5048.7 2162.66  5071.6 2166.75  5093.8 2167.82  5100.9 2168.66  5128.1 2169.51
  5189.1 2170.06  5218.5 2171.56  5280.5 2172.81  5339.3 2175.08  5380.8 2175.85
#Mann=3,-1,0
  4572.8    0.07       0  4993.6    0.05       0  5005.8    0.07       0
Bank Sta=4993.6,5005.8
Exp/Cntr=0.3,0.1

Type RM Length L Ch R = 1,7460,430,430,430
BEGIN DESCRIPTION:
Stream0146 8.0
END DESCRIPTION:
XS GIS Cut Line= 3
      1786625.03     13915975.01      1786975.00     13916075.00
      1787774.97     13915275.03
#Sta/Elev= 30
  4636.6 2181.26  4673.6 2179.23  4717.3 2175.27  4736.3 2175.05  4758.2 2172.53
  4792.2 2172.06  4835.9 2166.86  4867.4 2164.88  4942.7 2162.41  4973.3 2158.88
  4973.8 2158.38  4985.7 2158.88  5035.5 2158.91  5073.7 2161.64  5191.9 2167.40
  5262.3 2167.20  5361.6 2169.44  5430.3 2169.33  5620.5 2174.55  5641.7 2175.97
  5744.4 2179.42  5756.7 2178.75  5824.2 2182.41  5836.9 2182.15  5841.2 2182.95
  5926.9 2185.96  5985.4 2189.23  6011.7 2189.09  6100.9 2194.34  6131.9 2195.14
#Mann=3,-1,0
  4636.6    0.07       0  4973.3    0.05       0  4985.7    0.07       0
Bank Sta=4973.3,4985.7
Exp/Cntr=0.3,0.1