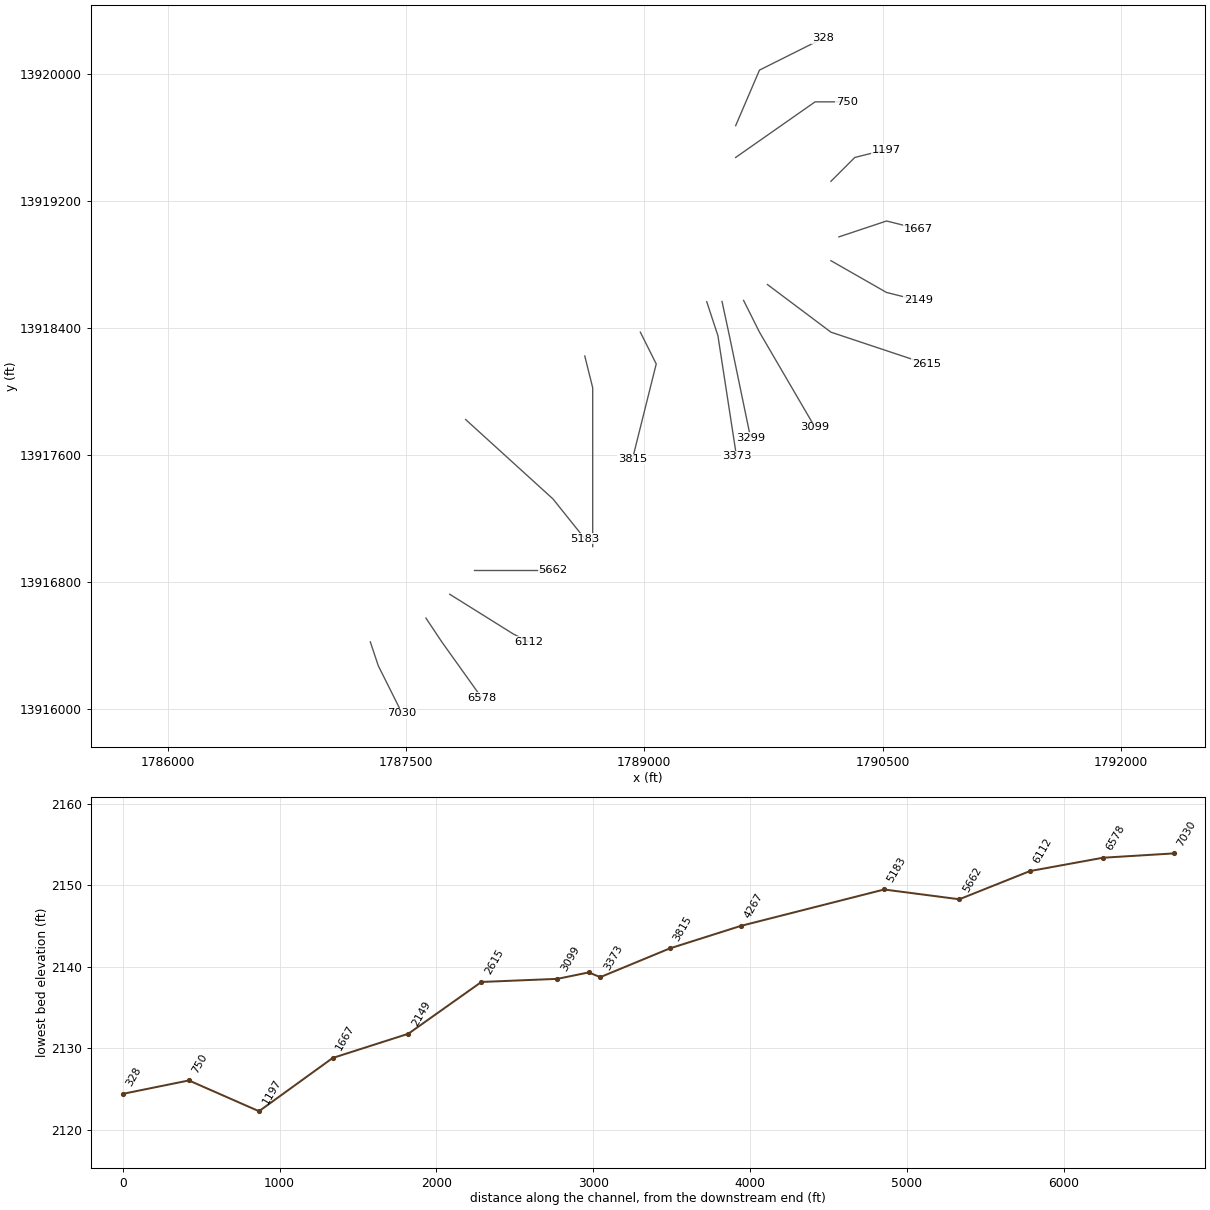
HEC-RAS study Stream0146.prj: Stream0146 Base Level Engineering

--- Stream0146.g01 (geometry) --- (continued)

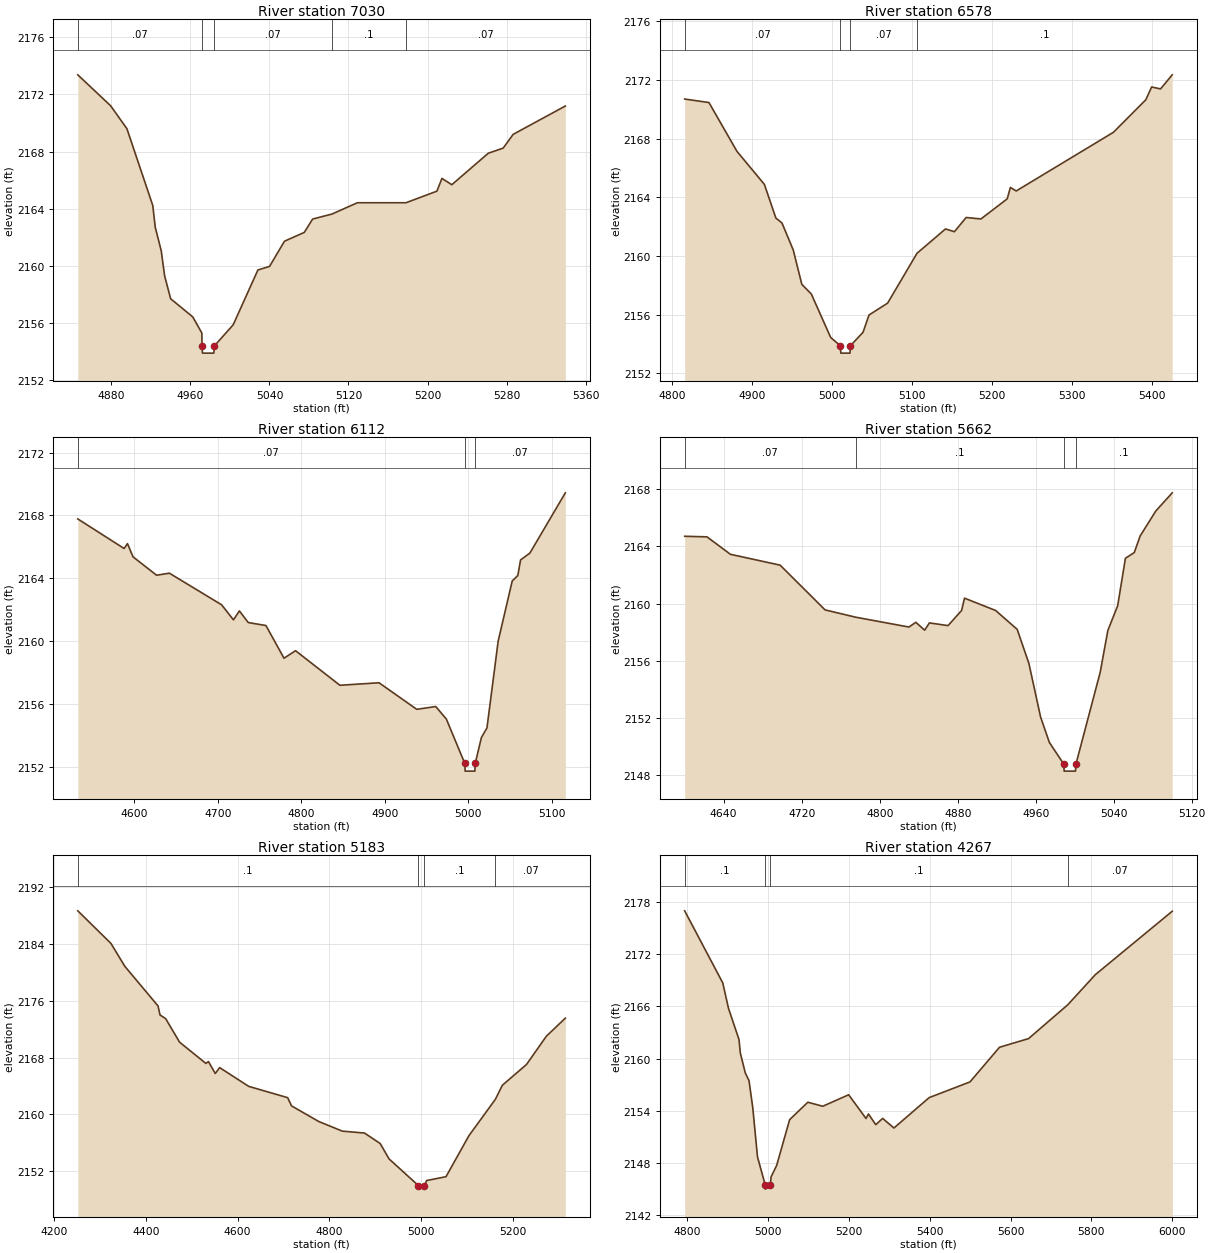
Type RM Length L Ch R = 1,7030,452,452,452
BEGIN DESCRIPTION:
Stream0146 7.0
END DESCRIPTION:
XS GIS Cut Line= 3
      1787274.99     13916425.02      1787325.00     13916275.00
      1787474.98     13915975.04
#Sta/Elev= 30
  4846.0 2173.36  4879.2 2171.20  4895.7 2169.60  4921.9 2164.23  4924.4 2162.71
  4930.5 2161.05  4933.9 2159.31  4940.0 2157.71  4962.4 2156.44  4971.6 2155.31
  4971.7 2154.41  4972.2 2153.91  4983.7 2153.91  4984.2 2154.41  5003.3 2155.89
  5028.3 2159.72  5040.1 2159.97  5055.2 2161.73  5075.3 2162.35  5083.7 2163.28
  5103.3 2163.63  5129.0 2164.42  5178.2 2164.42  5209.5 2165.23  5214.6 2166.12
  5224.6 2165.68  5261.5 2167.88  5276.6 2168.24  5286.7 2169.20  5339.5 2171.18
#Mann=5,-1,0
  4846.0    0.07       0  4971.7    0.05       0  4984.2    0.07       0
  5103.3     0.1       0  5178.2    0.07       0
Bank Sta=4971.7,4984.2
Exp/Cntr=0.3,0.1

Type RM Length L Ch R = 1,6578,466,466,466
BEGIN DESCRIPTION:
Stream0146 6.0
END DESCRIPTION:
XS GIS Cut Line= 3
      1787625.02     13916574.97      1787725.00     13916425.00
      1787975.02     13916074.97
#Sta/Elev= 30
  4815.5 2170.71  4845.9 2170.47  4881.0 2167.14  4915.3 2164.89  4929.7 2162.59
  4937.3 2162.26  4951.4 2160.42  4962.2 2158.07  4974.1 2157.41  4998.3 2154.45
  5010.5 2153.88  5011.0 2153.38  5022.5 2153.38  5023.0 2153.88  5038.8 2154.80
  5046.3 2155.98  5069.6 2156.79  5106.4 2160.19  5142.1 2161.85  5153.2 2161.66
  5167.9 2162.63  5186.4 2162.53  5219.3 2163.90  5223.3 2164.68  5230.6 2164.44
  5352.3 2168.44  5392.9 2170.66  5400.1 2171.53  5411.3 2171.40  5425.9 2172.36
#Mann=4,-1,0
  4815.5    0.07       0  5010.5    0.05       0  5023.0    0.07       0
  5106.4     0.1       0
Bank Sta=5010.5,5023
Exp/Cntr=0.3,0.1

Type RM Length L Ch R = 1,6112,450,450,450
BEGIN DESCRIPTION:
Stream0146 5.0
END DESCRIPTION:
XS GIS Cut Line= 3
      1787774.96     13916725.02      1788175.00     13916475.00
      1788274.96     13916425.02
#Sta/Elev= 30
  4532.5 2167.78  4587.9 2165.90  4592.0 2166.21  4598.6 2165.37  4626.8 2164.20
  4642.1 2164.33  4704.6 2162.32  4718.8 2161.36  4725.9 2161.93  4736.5 2161.19
  4757.7 2161.00  4779.3 2158.92  4793.1 2159.40  4846.2 2157.20  4893.0 2157.36
  4938.2 2155.67  4960.9 2155.85  4973.6 2155.05  4995.6 2152.24  4996.1 2151.74
  5007.7 2151.74  5008.2 2152.24  5015.5 2153.87  5022.2 2154.49  5035.6 2160.01
  5052.4 2163.83  5059.1 2164.18  5062.4 2165.17  5073.6 2165.61  5116.0 2169.44
#Mann=3,-1,0
  4532.5    0.07       0  4995.6    0.05       0  5008.2    0.07       0
Bank Sta=4995.6,5008.2
Exp/Cntr=0.3,0.1

Type RM Length L Ch R = 1,5662,479,479,479
BEGIN DESCRIPTION:
Stream0146 4.0
END DESCRIPTION:
XS GIS Cut Line= 3
      1787925.00     13916875.00      1788325.00     13916875.00
      1788425.00     13916875.00
#Sta/Elev= 30
  4600.0 2164.71  4622.9 2164.67  4646.9 2163.45  4697.9 2162.69  4744.0 2159.56
  4775.3 2159.05  4830.0 2158.36  4837.1 2158.69  4846.1 2158.14  4851.0 2158.65
  4870.1 2158.46  4884.0 2159.52  4887.0 2160.38  4918.9 2159.52  4941.0 2158.20
  4953.0 2155.82  4965.0 2152.07  4974.0 2150.29  4988.7 2148.78  4989.2 2148.28
  5000.8 2148.28  5001.3 2148.78  5026.1 2155.18  5034.0 2158.12  5044.1 2159.86
  5052.0 2163.17  5061.1 2163.57  5067.1 2164.73  5083.2 2166.48  5100.0 2167.75
#Mann=4,-1,0
  4600.0    0.07       0  4775.3     0.1       0  4988.7    0.05       0
  5001.3     0.1       0
Bank Sta=4988.7,5001.3
Exp/Cntr=0.3,0.1

Type RM Length L Ch R = 1,5183,916,916,916
BEGIN DESCRIPTION:
Stream0146 3.0
END DESCRIPTION:
XS GIS Cut Line= 3
      1787874.98     13917825.02      1788425.00     13917325.00
      1788625.01     13917074.99
#Sta/Elev= 30
  4251.3 2188.64  4323.7 2184.05  4353.8 2180.84  4426.3 2175.26  4430.7 2173.98
  4443.0 2173.47  4473.3 2170.16  4530.7 2167.17  4536.3 2167.43  4551.2 2165.75
  4560.7 2166.58  4624.1 2163.94  4709.1 2162.35  4717.6 2161.19  4777.1 2158.99
  4828.4 2157.64  4876.8 2157.37  4910.9 2155.90  4930.3 2153.73  4994.3 2149.98
  4994.8 2149.48  5007.1 2149.98  5012.3 2150.69  5054.5 2151.23  5104.5 2157.00
  5162.2 2162.12  5177.5 2164.10  5230.1 2167.02  5273.3 2170.99  5314.8 2173.54
#Mann=4,-1,0
  4251.3     0.1       0  4994.3    0.05       0  5007.1     0.1       0
  5162.2    0.07       0
Bank Sta=4994.3,5007.1
Exp/Cntr=0.3,0.1

Type RM Length L Ch R = 1,4267,452,452,452
BEGIN DESCRIPTION:
Stream0146 2.0
END DESCRIPTION:
XS GIS Cut Line= 3
      1788625.01     13918224.96      1788675.00     13918025.00
      1788675.00     13917025.02
#Sta/Elev= 30
  4793.9 2177.00  4888.2 2168.71  4902.3 2165.79  4928.4 2162.19  4931.5 2160.67
  4943.9 2158.36  4953.1 2157.47  4962.4 2154.36  4974.1 2148.70  4993.1 2145.50
  4993.6 2145.00  5005.9 2145.50  5007.6 2146.40  5021.5 2147.73  5053.6 2152.99
  5098.6 2154.99  5135.5 2154.53  5199.6 2155.85  5242.6 2153.12  5248.6 2153.64
  5266.6 2152.41  5283.7 2153.13  5311.6 2152.03  5398.7 2155.52  5499.8 2157.33
  5572.7 2161.31  5644.7 2162.31  5741.7 2166.20  5809.8 2169.66  6000.0 2176.95
#Mann=4,-1,0
  4793.9     0.1       0  4993.1    0.05       0  5005.9     0.1       0
  5741.7    0.07       0
Bank Sta=4993.1,5005.9
Exp/Cntr=0.3,0.1

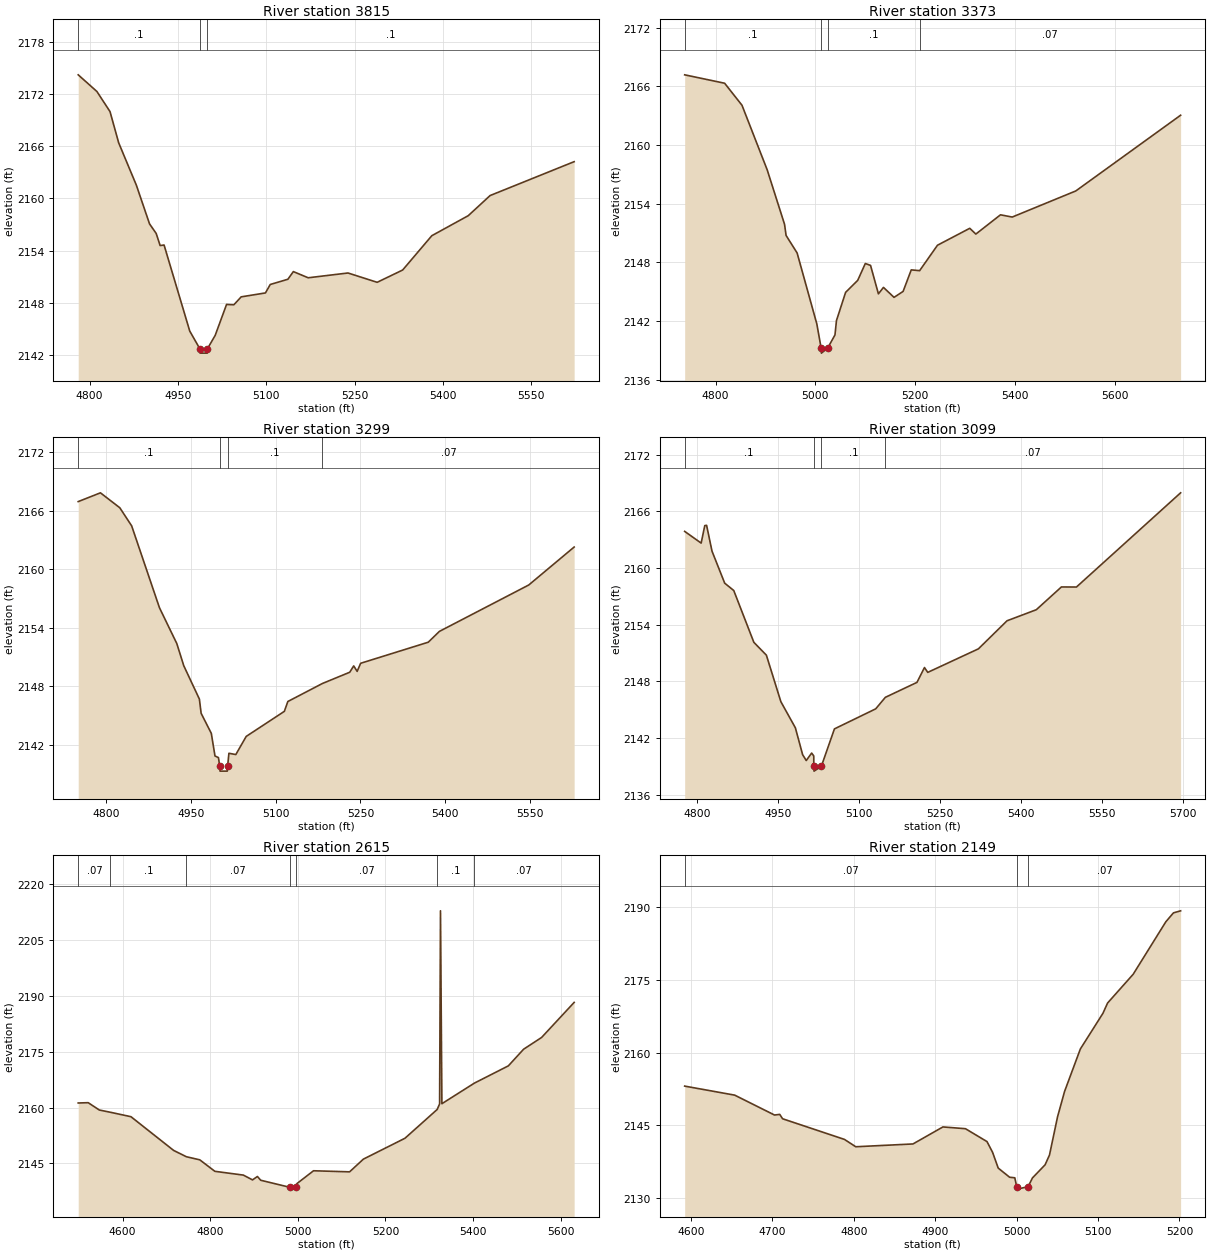
Type RM Length L Ch R = 1,3815,442,442,442
BEGIN DESCRIPTION:
Stream0146 1.0
END DESCRIPTION:
XS GIS Cut Line= 3
      1788975.00     13918375.00      1789075.00     13918175.00
      1788924.99     13917574.97
#Sta/Elev= 30
  4780.6 2174.19  4812.3 2172.28  4834.6 2169.97  4849.3 2166.39  4879.4 2161.51
  4901.7 2157.08  4913.0 2155.98  4919.7 2154.59  4926.4 2154.65  4970.0 2144.77
  4987.1 2142.74  4987.6 2142.24  4999.5 2142.24  5000.0 2142.74  5013.2 2144.28
  5032.5 2147.83  5044.9 2147.79  5057.3 2148.70  5098.5 2149.15  5106.7 2150.12
  5136.6 2150.72  5145.9 2151.60  5171.1 2150.89  5238.7 2151.44  5288.2 2150.37
  5331.5 2151.78  5381.0 2155.72  5442.9 2158.02  5480.0 2160.33  5622.7 2164.22
#Mann=3,-1,0
  4780.6     0.1       0  4987.1    0.05       0  5000.0     0.1       0
Bank Sta=4987.1,5000
Exp/Cntr=0.3,0.1

Type RM Length L Ch R = 1,3373,74,74,74
BEGIN DESCRIPTION:
Stream0146 0.0
END DESCRIPTION:
XS GIS Cut Line= 3
      1789392.95     13918566.77      1789463.26     13918353.23
      1789580.45     13917592.83
#Sta/Elev= 30
  4738.2 2167.17  4818.3 2166.31  4853.1 2164.06  4903.6 2157.46  4938.4 2151.89
  4941.5 2150.75  4963.6 2148.96  5003.1 2141.71  5011.8 2139.22  5012.3 2138.72
  5024.7 2139.22  5039.5 2140.58  5042.5 2142.05  5060.8 2144.93  5085.1 2146.16
  5100.3 2147.88  5110.8 2147.69  5126.6 2144.78  5136.7 2145.44  5157.9 2144.42
  5176.1 2145.03  5192.4 2147.23  5209.2 2147.15  5245.0 2149.75  5309.7 2151.48
  5321.9 2150.89  5371.3 2152.86  5394.8 2152.63  5522.3 2155.30  5732.4 2163.04
#Mann=4,-1,0
  4738.2     0.1       0  5011.8    0.05       0  5024.7     0.1       0
  5209.2    0.07       0
Bank Sta=5011.8,5024.7
Exp/Cntr=0.3,0.1

Type RM Length L Ch R = 1,3299,200,200,200
BEGIN DESCRIPTION:
Flat Rock Creek 2 58.0
END DESCRIPTION:
XS GIS Cut Line= 3
      1789489.29     13918568.11      1789538.78     13918337.61
      1789668.98     13917710.03
#Sta/Elev= 30
  4751.2 2166.94  4790.5 2167.84  4824.7 2166.31  4845.7 2164.45  4894.8 2156.06
  4925.5 2152.38  4937.8 2150.11  4965.4 2146.69  4968.5 2145.23  4986.5 2143.17
  4993.0 2140.85  4999.1 2140.69  5001.4 2139.80  5001.9 2139.30  5014.8 2139.30
  5015.3 2139.80  5017.6 2141.13  5029.8 2141.00  5048.2 2142.86  5115.6 2145.43
  5121.8 2146.44  5183.0 2148.29  5231.2 2149.44  5238.2 2150.09  5244.3 2149.53
  5250.5 2150.36  5370.0 2152.52  5389.7 2153.63  5547.7 2158.39  5627.9 2162.28
#Mann=4,-1,0
  4751.2     0.1       0  5001.4    0.05       0  5015.3     0.1       0
  5183.0    0.07       0
Bank Sta=5001.4,5015.3
Exp/Cntr=0.3,0.1

Type RM Length L Ch R = 1,3099,484,484,484
BEGIN DESCRIPTION:
Flat Rock Creek 2 57.0
END DESCRIPTION:
XS GIS Cut Line= 3
      1789624.99     13918575.02      1789725.00     13918375.00
      1790075.02     13917774.96
#Sta/Elev= 30
  4776.8 2163.88  4807.3 2162.64  4814.0 2164.49  4817.4 2164.52  4827.4 2161.79
  4850.9 2158.40  4867.7 2157.62  4904.9 2152.14  4928.1 2150.78  4954.9 2145.86
  4981.8 2143.09  4995.2 2140.25  5001.9 2139.63  5011.9 2140.42  5015.8 2140.12
  5015.9 2139.01  5016.4 2138.51  5029.8 2139.01  5054.1 2142.98  5130.5 2145.10
  5148.4 2146.32  5206.9 2147.90  5220.8 2149.47  5226.9 2148.96  5320.7 2151.45
  5373.7 2154.42  5427.9 2155.59  5474.4 2158.00  5502.2 2157.99  5695.1 2167.96
#Mann=4,-1,0
  4776.8     0.1       0  5015.9    0.05       0  5029.8     0.1       0
  5148.4    0.07       0
Bank Sta=5015.9,5029.8
Exp/Cntr=0.3,0.1

Type RM Length L Ch R = 1,2615,466,466,466
BEGIN DESCRIPTION:
Flat Rock Creek 2 56.0
END DESCRIPTION:
XS GIS Cut Line= 3
      1789775.02     13918674.99      1790175.00     13918375.00
      1790774.97     13918175.01
#Sta/Elev= 30
  4498.5 2161.21  4521.3 2161.29  4546.7 2159.33  4572.1 2158.72  4618.9 2157.54
  4716.4 2148.50  4745.5 2146.81  4776.1 2145.98  4810.6 2142.90  4875.6 2141.89
  4896.5 2140.60  4907.7 2141.52  4915.2 2140.51  4981.3 2138.63  4981.8 2138.13
  4995.3 2138.63  4997.8 2139.60  5035.8 2143.05  5118.1 2142.76  5149.7 2146.17
  5244.6 2151.76  5318.1 2159.47  5323.7 2160.96  5325.7 2212.70  5328.9 2161.02
  5403.2 2166.54  5480.7 2171.16  5515.5 2175.62  5556.6 2178.77  5630.9 2188.16
#Mann=7,-1,0
  4498.5    0.07       0  4572.1     0.1       0  4745.5    0.07       0
  4981.3    0.05       0  4995.3    0.07       0  5318.1     0.1       0
  5403.2    0.07       0
Bank Sta=4981.3,4995.3
Exp/Cntr=0.3,0.1

Type RM Length L Ch R = 1,2149,482,482,482
BEGIN DESCRIPTION:
Flat Rock Creek 2 55.0
END DESCRIPTION:
XS GIS Cut Line= 3
      1790174.98     13918825.01      1790525.00     13918625.00
      1790725.01     13918575.00
#Sta/Elev= 30
  4592.2 2153.07  4653.7 2151.20  4702.6 2147.09  4709.0 2147.22  4712.5 2146.32
  4788.5 2142.05  4802.4 2140.53  4872.7 2141.11  4909.5 2144.63  4937.2 2144.26
  4963.6 2141.60  4970.5 2139.38  4977.4 2136.12  4991.4 2134.23  4997.8 2134.11
  5000.1 2132.27  5000.6 2131.77  5014.1 2132.27  5019.5 2134.09  5035.0 2136.80
  5040.4 2138.82  5050.3 2146.72  5058.9 2151.95  5078.3 2160.74  5106.1 2168.13
  5111.7 2170.23  5143.2 2176.19  5183.4 2187.06  5192.7 2188.89  5201.5 2189.31
#Mann=3,-1,0
  4592.2    0.07       0  5000.1    0.05       0  5014.1    0.07       0
Bank Sta=5000.1,5014.1
Exp/Cntr=0.3,0.1

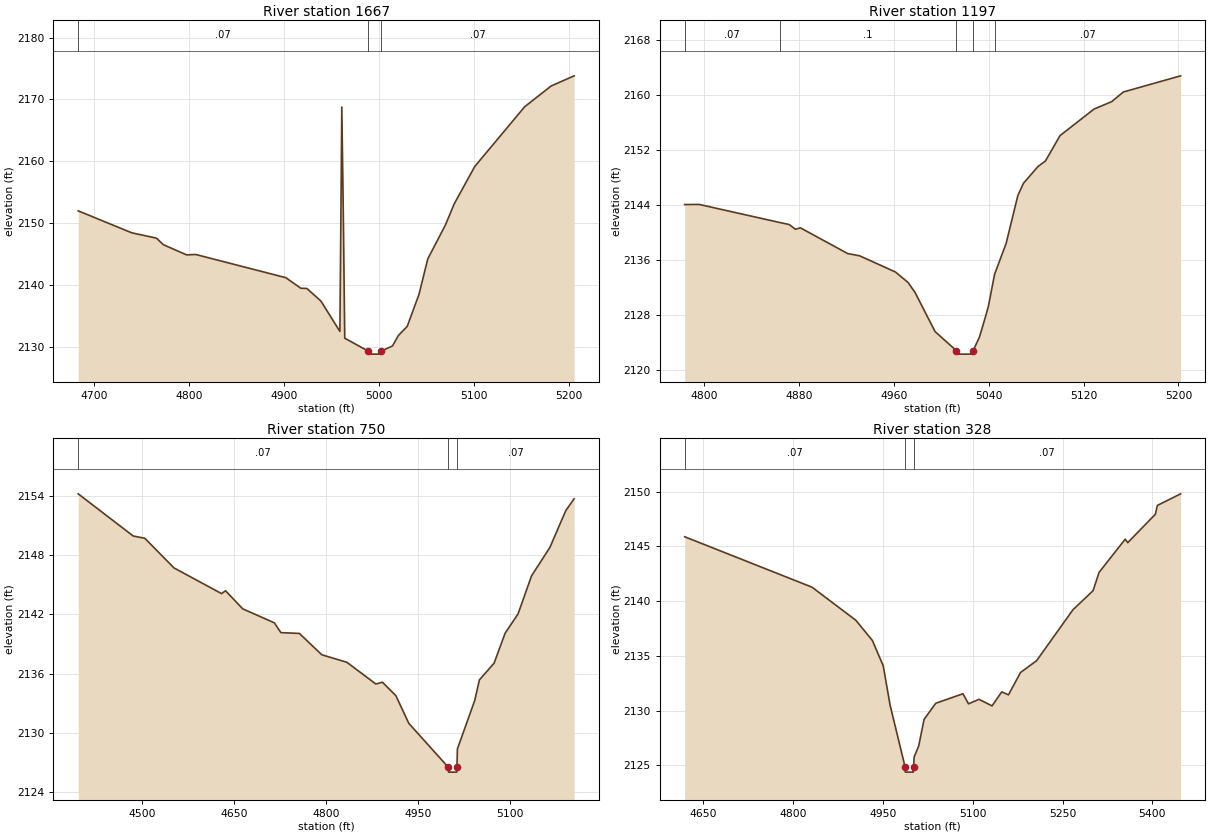
Type RM Length L Ch R = 1,1667,470,470,470
BEGIN DESCRIPTION:
Flat Rock Creek 2 54.0
END DESCRIPTION:
XS GIS Cut Line= 3
      1790225.04     13918975.01      1790525.00     13919075.00
      1790724.96     13919025.01
#Sta/Elev= 30
  4683.4 2151.98  4739.7 2148.43  4765.8 2147.56  4773.0 2146.51  4797.6 2144.85
  4807.1 2144.92  4902.0 2141.17  4917.8 2139.46  4924.2 2139.42  4939.0 2137.39
  4959.0 2132.47  4960.3 2155.49  4961.0 2168.77  4962.6 2151.45  4964.1 2131.38
  4988.7 2129.30  4989.2 2128.80  5002.3 2128.80  5002.8 2129.30  5014.4 2130.13
  5020.6 2131.81  5029.9 2133.29  5042.3 2138.47  5051.5 2144.19  5070.1 2149.68
  5079.4 2153.11  5101.0 2159.15  5153.6 2168.82  5181.5 2172.18  5205.7 2173.82
#Mann=3,-1,0
  4683.4    0.07       0  4988.7    0.05       0  5002.8    0.07       0
Bank Sta=4988.7,5002.8
Exp/Cntr=0.3,0.1

Type RM Length L Ch R = 1,1197,447,447,447
BEGIN DESCRIPTION:
Flat Rock Creek 2 53.0
END DESCRIPTION:
XS GIS Cut Line= 3
      1790175.00     13919325.00      1790325.00     13919475.00
      1790525.01     13919525.00
#Sta/Elev= 30
  4783.5 2144.01  4795.8 2144.02  4863.8 2141.39  4871.7 2141.10  4876.9 2140.41
  4881.1 2140.62  4921.0 2136.88  4931.1 2136.55  4961.3 2134.20  4971.9 2132.68
  4977.8 2131.22  4994.7 2125.54  5012.7 2122.76  5013.2 2122.26  5026.3 2122.26
  5026.8 2122.76  5032.1 2124.72  5037.2 2127.68  5039.7 2129.24  5044.9 2133.88
  5054.6 2138.33  5064.5 2145.31  5069.2 2147.09  5081.6 2149.55  5087.8 2150.34
  5100.1 2154.03  5128.8 2157.89  5143.7 2158.97  5153.5 2160.37  5201.8 2162.72
#Mann=5,-1,0
  4783.5    0.07       0  4863.8     0.1       0  5012.7    0.05       0
  5026.8     0.1       0  5044.9    0.07       0
Bank Sta=5012.7,5026.8
Exp/Cntr=0.3,0.1

Type RM Length L Ch R = 1,750,422,422,422
BEGIN DESCRIPTION:
Flat Rock Creek 2 52.0
END DESCRIPTION:
XS GIS Cut Line= 3
      1789574.97     13919474.98      1790075.00     13919825.00
      1790275.04     13919825.00
#Sta/Elev= 30
  4395.0 2154.21  4484.9 2149.94  4503.9 2149.71  4551.5 2146.71  4629.3 2144.11
  4635.7 2144.40  4663.8 2142.57  4715.5 2141.15  4726.2 2140.16  4756.4 2140.08
  4793.0 2137.92  4834.0 2137.16  4881.4 2134.96  4892.1 2135.14  4914.1 2133.78
  4935.3 2130.97  4999.7 2126.54  5000.2 2126.04  5013.4 2126.04  5013.9 2126.54
  5014.6 2128.38  5042.8 2133.27  5050.6 2135.38  5074.6 2137.07  5092.6 2140.10
  5113.7 2142.05  5135.8 2145.91  5165.8 2148.79  5191.7 2152.51  5205.4 2153.71
#Mann=3,-1,0
  4395.0    0.07       0  4999.7    0.05       0  5013.9    0.07       0
Bank Sta=4999.7,5013.9
Exp/Cntr=0.3,0.1

Type RM Length L Ch R = 1,328,0,0,0
BEGIN DESCRIPTION:
Flat Rock Creek 2 51.0
END DESCRIPTION:
XS GIS Cut Line= 3
      1789574.99     13919674.97      1789725.00     13920025.00
      1790124.97     13920224.98
#Sta/Elev= 30
  4619.2 2145.89  4831.9 2141.28  4905.0 2138.26  4932.5 2136.42  4950.7 2134.10
  4962.2 2130.50  4987.1 2124.89  4987.6 2124.39  5000.8 2124.39  5001.3 2124.89
  5002.4 2125.79  5009.9 2126.77  5018.9 2129.21  5038.4 2130.68  5083.8 2131.55
  5093.0 2130.63  5110.6 2131.04  5132.4 2130.44  5148.6 2131.72  5159.8 2131.45
  5179.9 2133.49  5206.8 2134.57  5267.4 2139.22  5301.0 2140.96  5311.1 2142.64
  5354.7 2145.67  5358.9 2145.35  5405.0 2147.94  5408.4 2148.75  5447.2 2149.81
#Mann=3,-1,0
  4619.2    0.07       0  4987.1    0.05       0  5001.3    0.07       0
Bank Sta=4987.1,5001.3
Exp/Cntr=0.3,0.1

Chan Stop Cuts=-1