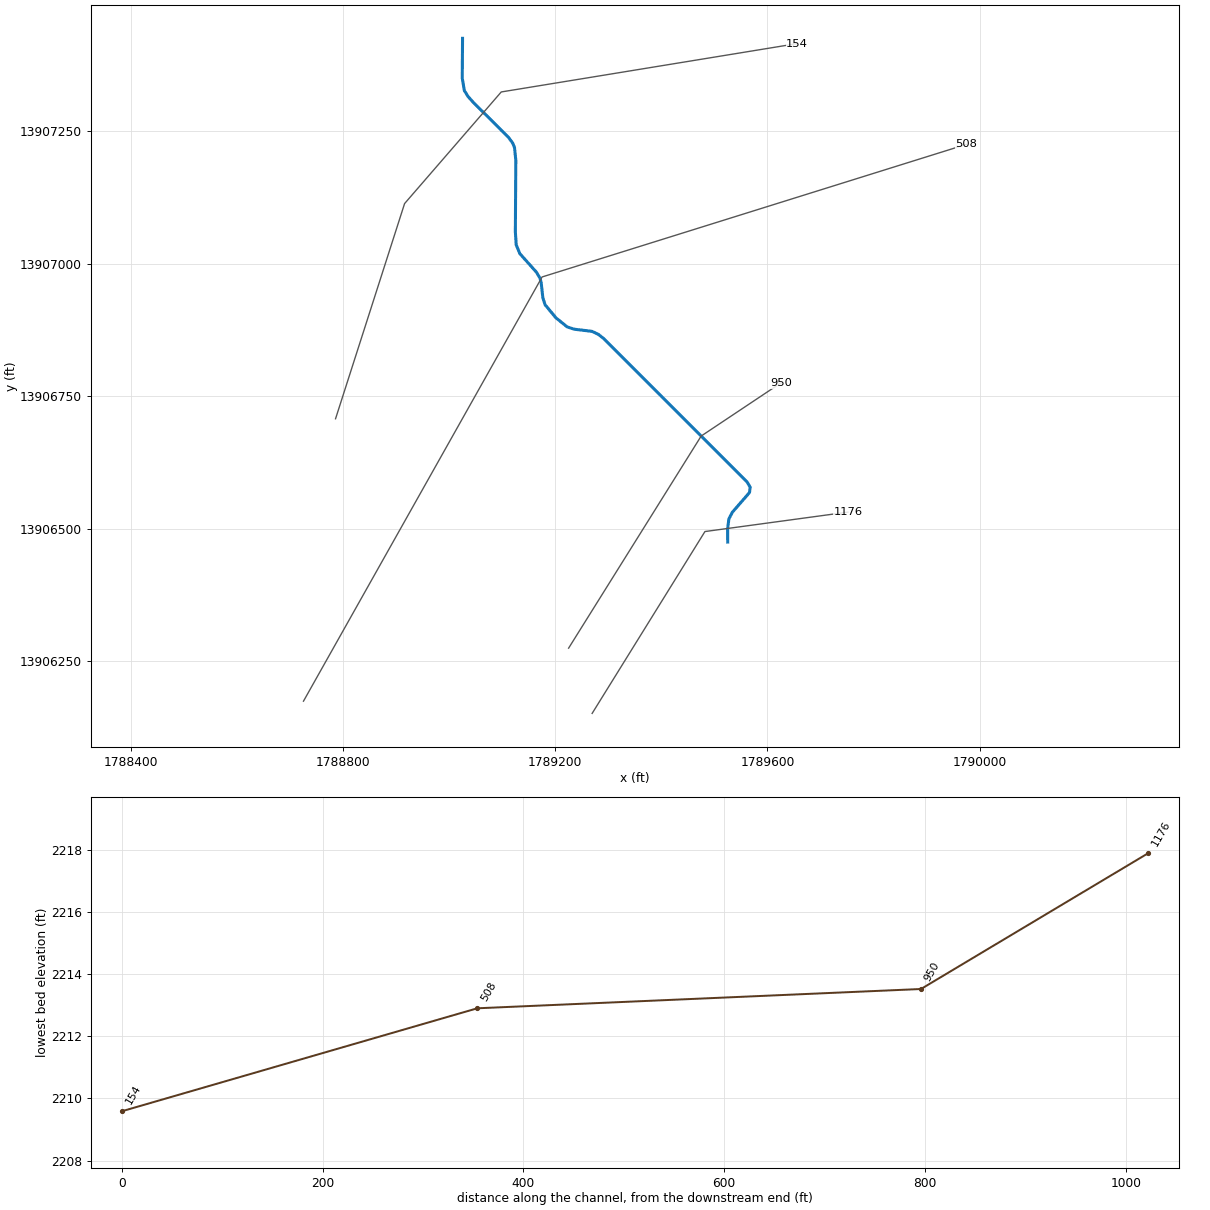
--- Stream0147.prj (project) ---

Proj Title=Stream0147 Base Level Engineering
Current Plan=p01
Default Exp/Contr=0.3,0.1
English Units
Geom File=g01
Flow File=f01
Plan File=p01
BEGIN DESCRIPTION:
Stream0147
END DESCRIPTION:

--- Stream0147.p01 (plan) ---

Plan Title=Multiple Run
Short Identifier=Multiple
Geom File=g01
Flow File=f01
Subcritical Flow
K Sum by GR= 0
Std Step Tol= 0.01
Critical Tol= 0.01
Num of Std Step Trials= 20
Max Error Tol= 0.3
Flow Tol Ratio= 0.001
Split Flow NTrial= 30
Split Flow Tol= 0.02
Split Flow Ratio= 0.02
Log Output Level= 0
Friction Slope Method= 1
Unsteady Friction Slope Method= 2
Unsteady Bridges Friction Slope Method= 1
Parabolic Critical Depth
Global Vel Dist=  1 , 1 , 1
Global Log Level= 0
CheckData=True
Encroach Param= -1, 0, 0, 0
BEGIN DESCRIPTION:
Multiple Run
END DESCRIPTION:

--- Stream0147.f01 (steady flow) ---

Flow Title=Multiple
Number of Profiles=7
Profile Names=10-year,25-year,50-year,1pct_min,100-year,1pct_plu,500-year
River Rch & RM= Stream0147,Reach-1,1176
    1084    1843    2561    1719    3429    6842    6082
Boundary for River Rch & Prof#=Stream0147,Reach-1,1
Up Type=0
Dn Type=3
Dn Slope=0.005
Boundary for River Rch & Prof#=Stream0147,Reach-1,2
Up Type=0
Dn Type=3
Dn Slope=0.005
Boundary for River Rch & Prof#=Stream0147,Reach-1,3
Up Type=0
Dn Type=3
Dn Slope=0.005
Boundary for River Rch & Prof#=Stream0147,Reach-1,4
Up Type=0
Dn Type=3
Dn Slope=0.005
Boundary for River Rch & Prof#=Stream0147,Reach-1,5
Up Type=0
Dn Type=3
Dn Slope=0.005
Boundary for River Rch & Prof#=Stream0147,Reach-1,6
Up Type=0
Dn Type=3
Dn Slope=0.005
Boundary for River Rch & Prof#=Stream0147,Reach-1,7
Up Type=0
Dn Type=3
Dn Slope=0.005

--- Stream0147.g01 (geometry) ---

Geom Title=Existing Conditions

River Reach=Stream0147,Reach-1
Reach XY= 30
      1789525.00     13906475.00      1789524.87     13906500.37
      1789527.30     13906518.86      1789533.74     13906531.21
      1789566.10     13906568.42      1789567.41     13906578.39
      1789561.54     13906588.37      1789291.66     13906858.34
      1789281.03     13906866.83      1789268.91     13906872.45
      1789235.49     13906876.49      1789222.46     13906880.75
      1789201.16     13906897.86      1789180.73     13906922.45
      1789176.44     13906935.47      1789173.26     13906964.24
      1789170.77     13906973.22      1789163.84     13906984.51
      1789133.09     13907018.92      1789126.20     13907035.50
      1789124.57     13907059.82      1789125.43     13907195.18
      1789122.93     13907219.14      1789119.53     13907227.45
      1789111.60     13907238.31      1789044.66     13907304.86
      1789035.46     13907315.19      1789028.39     13907326.41
      1789024.41     13907349.76      1789025.00     13907425.00

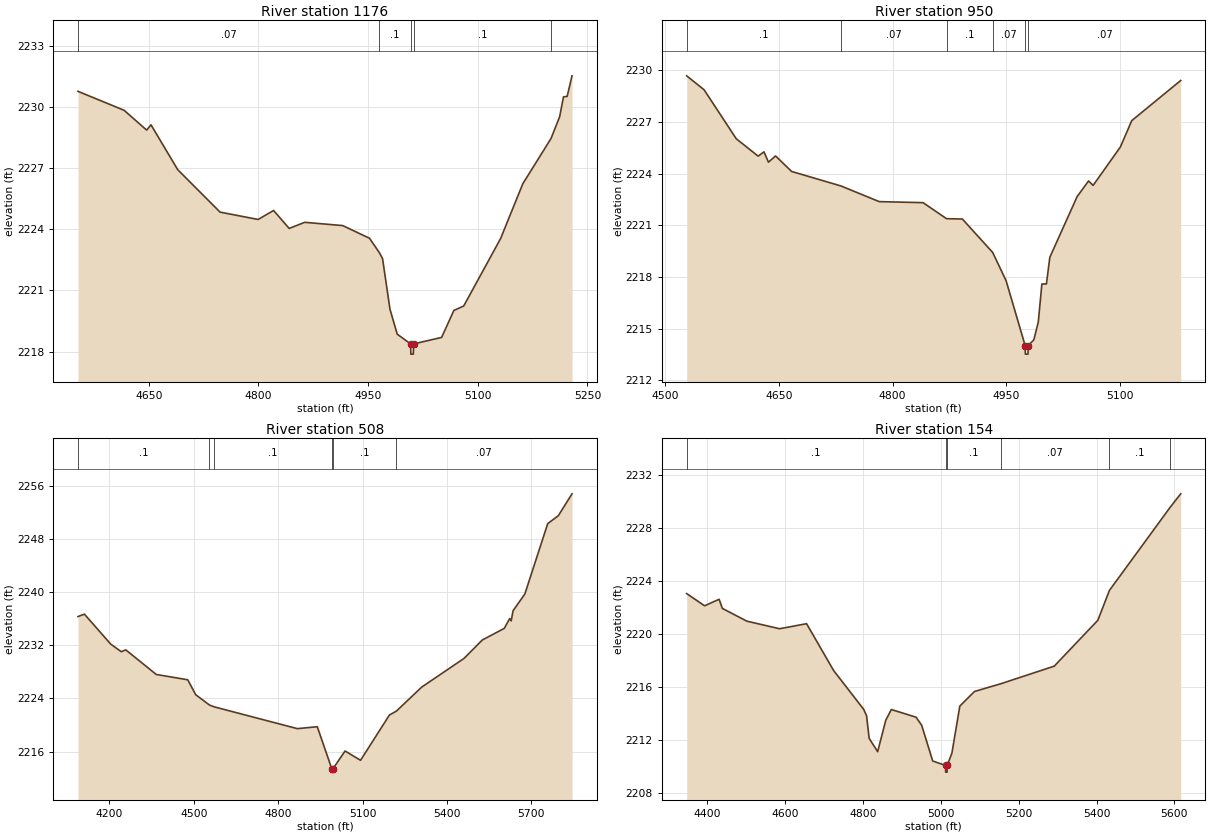
Type RM Length L Ch R = 1,1176,226,226,226
BEGIN DESCRIPTION:
Stream0147 3.0
END DESCRIPTION:
XS GIS Cut Line= 3
      1789269.41     13906152.01      1789482.09     13906494.90
      1789751.71     13906531.57
#Sta/Elev= 30
  4553.3 2230.76  4616.4 2229.83  4647.2 2228.86  4653.1 2229.12  4689.7 2226.92
  4747.6 2224.84  4799.6 2224.48  4820.8 2224.92  4842.1 2224.04  4863.3 2224.34
  4915.3 2224.18  4951.9 2223.56  4965.5 2222.85  4969.8 2222.56  4979.9 2220.09
  4989.8 2218.86  5008.2 2218.38  5008.4 2217.88  5011.9 2217.88  5012.2 2218.38
  5050.6 2218.70  5067.3 2220.02  5080.8 2220.24  5131.3 2223.55  5161.6 2226.23
  5200.2 2228.45  5212.0 2229.52  5217.2 2230.49  5222.2 2230.51  5228.9 2231.52
#Mann=5,-1,0
  4553.3    0.07       0  4965.5     0.1       0  5008.2    0.05       0
  5012.2     0.1       0  5200.2    0.07       0
Bank Sta=5008.2,5012.2
Exp/Cntr=0.3,0.1

Type RM Length L Ch R = 1,950,442,442,442
BEGIN DESCRIPTION:
Stream0147 2.0
END DESCRIPTION:
XS GIS Cut Line= 3
      1789225.02     13906275.03      1789475.00     13906675.00
      1789624.97     13906774.98
#Sta/Elev= 30
  4528.3 2229.67  4551.3 2228.86  4593.7 2226.02  4622.6 2225.01  4630.3 2225.26
  4636.2 2224.66  4645.6 2225.02  4666.8 2224.12  4731.8 2223.28  4782.4 2222.37
  4840.2 2222.31  4871.2 2221.38  4892.1 2221.36  4932.1 2219.42  4949.8 2217.78
  4974.9 2214.02  4975.2 2213.52  4978.7 2213.52  4979.0 2214.02  4986.4 2214.35
  4992.3 2215.39  4997.0 2217.59  5003.0 2217.59  5007.5 2219.14  5043.5 2222.66
  5058.6 2223.57  5064.6 2223.31  5100.6 2225.54  5115.6 2227.07  5180.2 2229.40
#Mann=6,-1,0
  4528.3     0.1       0  4731.8    0.07       0  4871.2     0.1       0
  4932.1    0.07       0  4974.9    0.05       0  4979.0    0.07       0
Bank Sta=4974.9,4979
Exp/Cntr=0.3,0.1

Type RM Length L Ch R = 1,508,354,354,354
BEGIN DESCRIPTION:
Stream0147 1.0
END DESCRIPTION:
XS GIS Cut Line= 3
      1788725.01     13906175.01      1789175.00     13906975.00
      1789974.98     13907224.99
#Sta/Elev= 30
  4088.3 2236.30  4111.2 2236.66  4204.6 2232.16  4242.2 2231.01  4258.2 2231.29
  4366.5 2227.59  4478.4 2226.79  4506.8 2224.54  4555.7 2222.99  4573.1 2222.71
  4868.2 2219.44  4938.9 2219.73  4990.4 2213.40  4990.7 2212.90  4994.5 2213.40
  5037.6 2216.08  5092.6 2214.68  5195.3 2221.49  5220.1 2222.08  5310.0 2225.69
  5460.3 2230.00  5525.3 2232.77  5603.4 2234.52  5622.7 2236.00  5628.0 2235.65
  5634.8 2237.18  5676.7 2239.70  5757.9 2250.28  5795.6 2251.47  5844.3 2254.76
#Mann=6,-1,0
  4088.3     0.1       0  4555.7    0.07       0  4573.1     0.1       0
  4990.4    0.05       0  4994.5     0.1       0  5220.1    0.07       0
Bank Sta=4990.4,4994.5
Exp/Cntr=0.3,0.1

Type RM Length L Ch R = 1,154,0,0,0
BEGIN DESCRIPTION:
Stream0147 0.0
END DESCRIPTION:
XS GIS Cut Line= 4
      1788785.48     13906707.58      1788915.68     13907113.39
      1789097.97     13907323.89      1789655.72     13907415.05
#Sta/Elev= 30
  4346.5 2223.05  4392.5 2222.13  4429.9 2222.62  4438.3 2221.93  4501.3 2220.97
  4585.3 2220.40  4654.7 2220.78  4724.2 2217.25  4801.3 2214.33  4808.9 2213.84
  4815.5 2212.14  4837.4 2211.13  4858.2 2213.50  4872.5 2214.31  4936.1 2213.73
  4950.4 2213.13  4978.9 2210.43  5011.9 2210.09  5012.2 2209.59  5015.8 2209.59
  5016.0 2210.09  5028.2 2211.02  5048.6 2214.57  5086.3 2215.67  5154.7 2216.26
  5291.3 2217.58  5403.4 2221.04  5433.1 2223.29  5588.8 2229.54  5616.3 2230.57
#Mann=6,-1,0
  4346.5     0.1       0  5011.9    0.05       0  5016.0     0.1       0
  5154.7    0.07       0  5433.1     0.1       0  5588.8    0.07       0
Bank Sta=5011.9,5016
Exp/Cntr=0.3,0.1

Chan Stop Cuts=-1