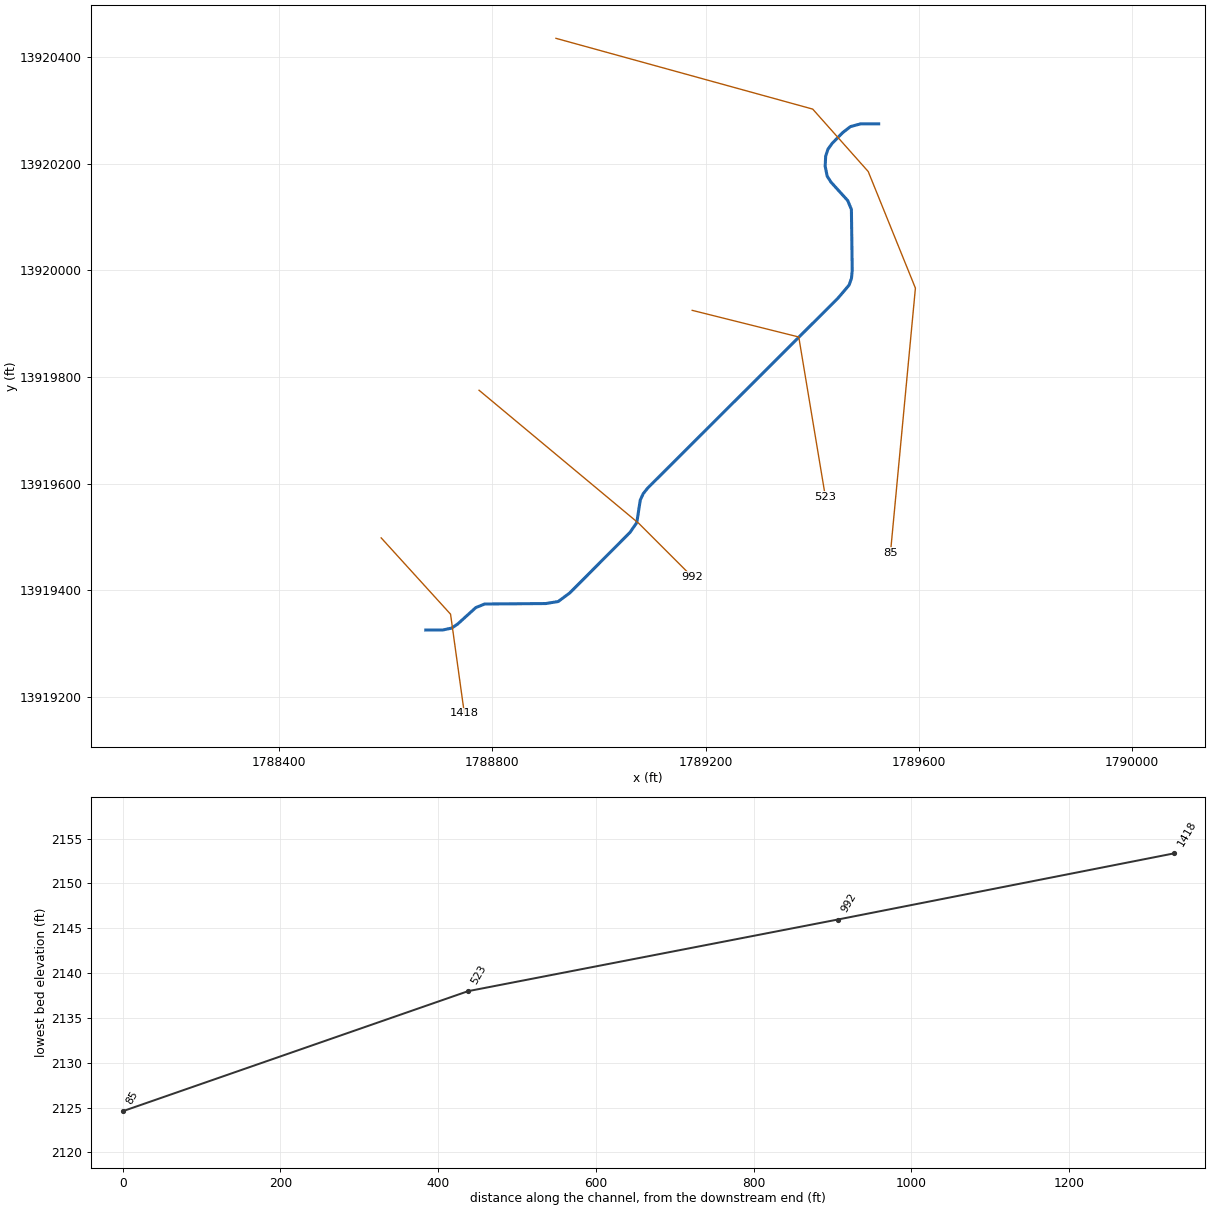
--- Stream0152.prj (project) ---

Proj Title=Stream0152 Base Level Engineering
Current Plan=p01
Default Exp/Contr=0.3,0.1
English Units
Geom File=g01
Flow File=f01
Plan File=p01
BEGIN DESCRIPTION:
Stream0152
END DESCRIPTION:

--- Stream0152.p01 (plan) ---

Plan Title=Multiple Run
Short Identifier=Multiple
Geom File=g01
Flow File=f01
Subcritical Flow
K Sum by GR= 0
Std Step Tol= 0.01
Critical Tol= 0.01
Num of Std Step Trials= 20
Max Error Tol= 0.3
Flow Tol Ratio= 0.001
Split Flow NTrial= 30
Split Flow Tol= 0.02
Split Flow Ratio= 0.02
Log Output Level= 0
Friction Slope Method= 1
Unsteady Friction Slope Method= 2
Unsteady Bridges Friction Slope Method= 1
Parabolic Critical Depth
Global Vel Dist=  1 , 1 , 1
Global Log Level= 0
CheckData=True
Encroach Param= -1, 0, 0, 0
BEGIN DESCRIPTION:
Multiple Run
END DESCRIPTION:

--- Stream0152.f01 (steady flow) ---

Flow Title=Multiple
Number of Profiles=7
Profile Names=10-year,25-year,50-year,1pct_min,100-year,1pct_plu,500-year
River Rch & RM= Stream0152,Reach-1,1418
     373     599     800     520    1037    2069    1714
Boundary for River Rch & Prof#=Stream0152,Reach-1,1
Up Type=0
Dn Type=3
Dn Slope=0.005
Boundary for River Rch & Prof#=Stream0152,Reach-1,2
Up Type=0
Dn Type=3
Dn Slope=0.005
Boundary for River Rch & Prof#=Stream0152,Reach-1,3
Up Type=0
Dn Type=3
Dn Slope=0.005
Boundary for River Rch & Prof#=Stream0152,Reach-1,4
Up Type=0
Dn Type=3
Dn Slope=0.005
Boundary for River Rch & Prof#=Stream0152,Reach-1,5
Up Type=0
Dn Type=3
Dn Slope=0.005
Boundary for River Rch & Prof#=Stream0152,Reach-1,6
Up Type=0
Dn Type=3
Dn Slope=0.005
Boundary for River Rch & Prof#=Stream0152,Reach-1,7
Up Type=0
Dn Type=3
Dn Slope=0.005

--- Stream0152.g01 (geometry) ---

Geom Title=Existing Conditions

River Reach=Stream0152,Reach-1
Reach XY= 30
      1788675.00     13919325.00      1788706.80     13919325.12
      1788723.49     13919328.65      1788734.56     13919336.06
      1788768.84     13919367.10      1788785.47     13919373.87
      1788900.11     13919374.73      1788923.53     13919378.54
      1788945.16     13919394.61      1789058.35     13919508.33
      1789071.02     13919526.65      1789077.53     13919568.95
      1789083.16     13919581.05      1789091.65     13919591.67
      1789448.84     13919948.13      1789469.55     13919972.55
      1789473.96     13919985.44      1789475.32     13919999.89
      1789473.78     13920114.50      1789466.82     13920131.08
      1789435.55     13920165.49      1789428.33     13920176.76
      1789424.59     13920195.25      1789425.46     13920214.49
      1789429.85     13920227.52      1789437.80     13920238.55
      1789457.53     13920258.64      1789472.00     13920269.85
      1789491.14     13920275.01      1789525.00     13920275.00

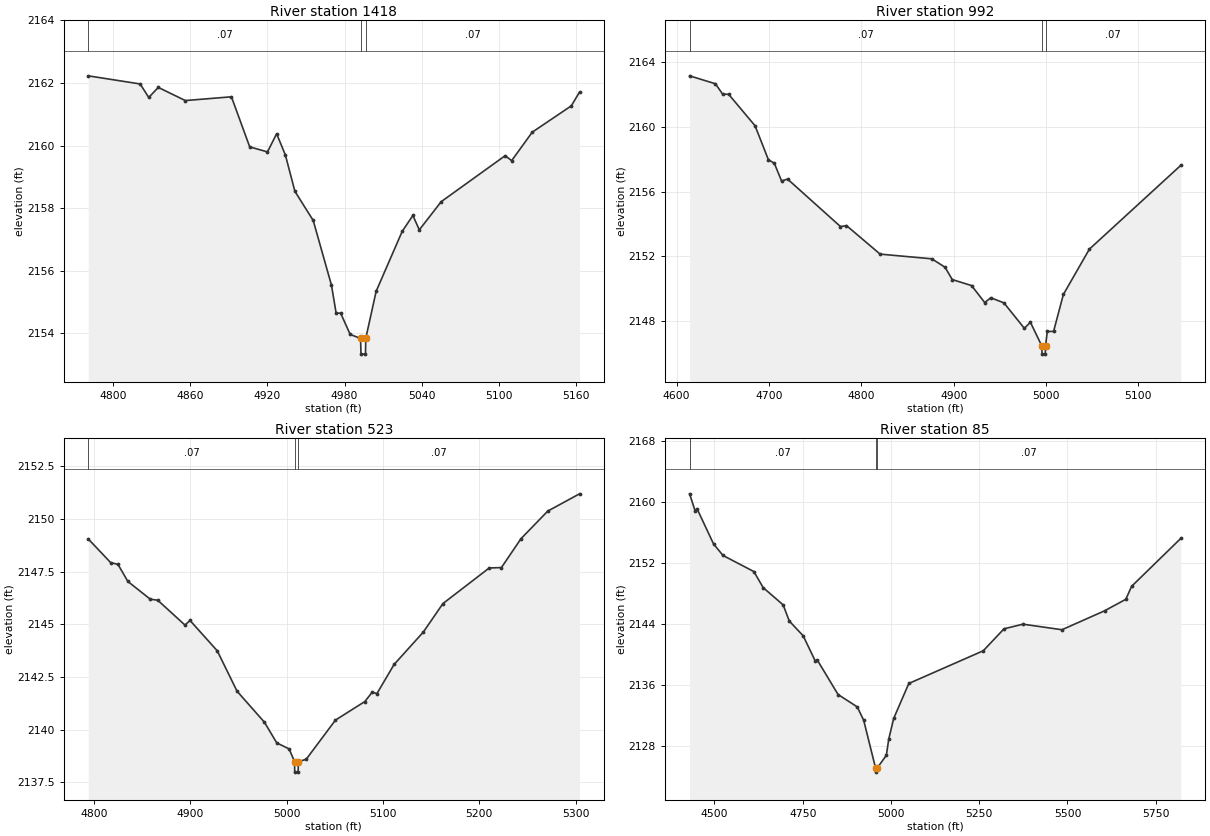
Type RM Length L Ch R = 1,1418,426,426,426
BEGIN DESCRIPTION:
Stream0152 3.0
END DESCRIPTION:
XS GIS Cut Line= 3
      1788591.29     13919497.99      1788721.51     13919354.75
      1788747.36     13919168.62
#Sta/Elev= 30
  4780.9 2162.23  4821.2 2161.97  4827.9 2161.54  4835.3 2161.86  4856.3 2161.44
  4892.1 2161.56  4906.3 2159.96  4920.1 2159.80  4927.2 2160.38  4934.0 2159.70
  4941.4 2158.54  4955.6 2157.61  4969.8 2155.54  4973.4 2154.65  4976.9 2154.65
  4984.3 2153.97  4992.4 2153.84  4992.7 2153.34  4996.2 2153.34  4996.4 2153.84
  5004.5 2155.35  5024.7 2157.26  5033.0 2157.77  5038.0 2157.31  5055.0 2158.21
  5104.7 2159.68  5109.7 2159.52  5125.7 2160.43  5156.0 2161.27  5162.4 2161.71
#Mann=3,-1,0
  4780.9    0.07       0  4992.4    0.05       0  4996.4    0.07       0
Bank Sta=4992.4,4996.4
Exp/Cntr=0.3,0.1

Type RM Length L Ch R = 1,992,469,469,469
BEGIN DESCRIPTION:
Stream0152 2.0
END DESCRIPTION:
XS GIS Cut Line= 3
      1788775.00     13919775.00      1789075.00     13919525.00
      1789174.97     13919425.03
#Sta/Elev= 30
  4614.1 2163.14  4642.1 2162.65  4649.9 2162.01  4656.4 2162.00  4685.0 2160.06
  4699.4 2157.97  4705.9 2157.74  4713.7 2156.65  4720.2 2156.77  4777.5 2153.84
  4784.0 2153.90  4820.4 2152.14  4876.4 2151.85  4890.7 2151.33  4898.5 2150.57
  4919.4 2150.20  4933.7 2149.15  4940.2 2149.45  4954.5 2149.13  4976.6 2147.56
  4983.1 2147.94  4995.5 2146.47  4995.7 2145.97  4999.2 2145.97  4999.5 2146.47
  5001.4 2147.37  5008.2 2147.37  5018.8 2149.65  5047.0 2152.45  5146.0 2157.62
#Mann=3,-1,0
  4614.1    0.07       0  4995.5    0.05       0  4999.5    0.07       0
Bank Sta=4995.5,4999.5
Exp/Cntr=0.3,0.1

Type RM Length L Ch R = 1,523,438,438,438
BEGIN DESCRIPTION:
Stream0152 1.0
END DESCRIPTION:
XS GIS Cut Line= 3
      1789175.00     13919925.00      1789375.00     13919875.00
      1789425.00     13919574.99
#Sta/Elev= 30
  4793.8 2149.05  4817.0 2147.93  4824.7 2147.84  4835.0 2147.03  4858.2 2146.19
  4866.0 2146.14  4894.3 2144.96  4899.5 2145.18  4927.8 2143.74  4948.4 2141.82
  4976.8 2140.35  4989.6 2139.37  5002.5 2139.08  5008.1 2138.48  5008.3 2137.98
  5011.8 2137.98  5012.1 2138.48  5020.2 2138.59  5050.6 2140.45  5081.1 2141.33
  5088.7 2141.77  5093.7 2141.71  5111.5 2143.09  5141.9 2144.63  5162.2 2145.98
  5210.3 2147.67  5223.0 2147.69  5243.3 2149.06  5271.1 2150.37  5304.1 2151.19
#Mann=3,-1,0
  4793.8    0.07       0  5008.1    0.05       0  5012.1    0.07       0
Bank Sta=5008.1,5012.1
Exp/Cntr=0.3,0.1

Type RM Length L Ch R = 1,85,0,0,0
BEGIN DESCRIPTION:
Stream0152 0.0
END DESCRIPTION:
XS GIS Cut Line= 5
      1788919.39     13920435.49      1789401.19     13920302.67
      1789505.36     13920185.48      1789593.90     13919966.73
      1789547.06     13919469.69
#Sta/Elev= 30
  4429.4 2161.10  4445.2 2158.86  4450.4 2159.16  4497.5 2154.51  4524.3 2153.01
  4611.6 2150.90  4637.8 2148.80  4694.5 2146.53  4711.8 2144.42  4751.3 2142.47
  4785.7 2139.15  4790.9 2139.32  4850.1 2134.77  4904.4 2133.15  4922.7 2131.39
  4956.5 2125.09  4956.7 2124.59  4960.5 2125.09  4986.9 2126.80  4993.6 2128.91
  5007.8 2131.65  5050.5 2136.22  5261.4 2140.51  5320.2 2143.39  5373.9 2144.00
  5484.4 2143.27  5604.9 2145.75  5665.2 2147.26  5681.8 2148.97  5821.2 2155.26
#Mann=3,-1,0
  4429.4    0.07       0  4956.5    0.05       0  4960.5    0.07       0
Bank Sta=4956.5,4960.5
Exp/Cntr=0.3,0.1

Chan Stop Cuts=-1