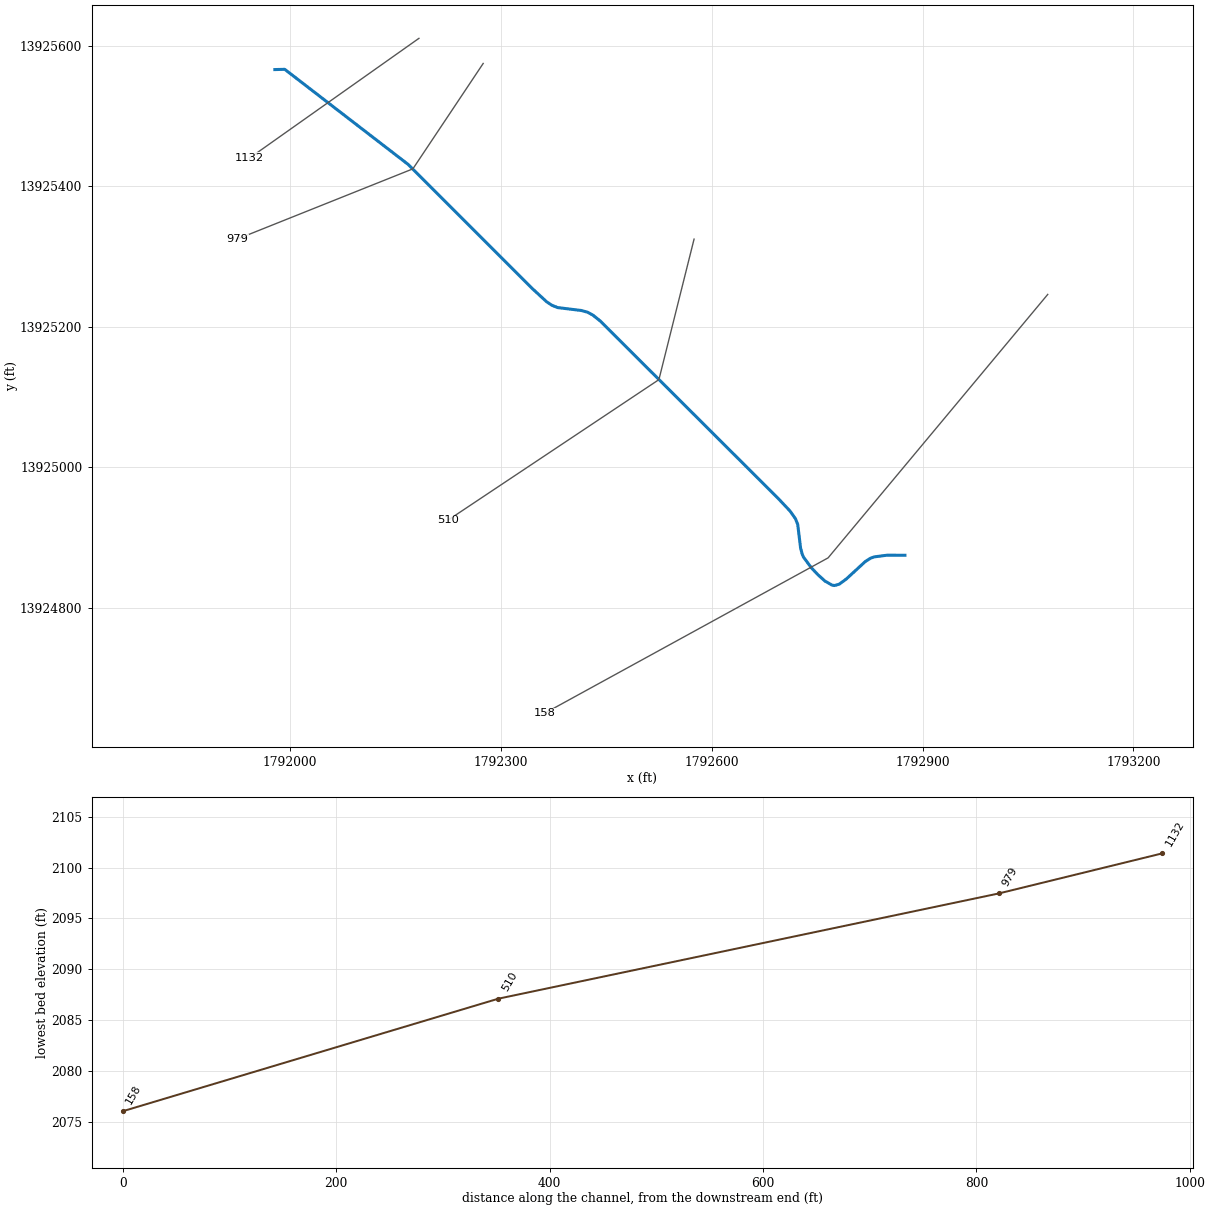
--- Stream0155.prj (project) ---

Proj Title=Stream0155 Base Level Engineering
Current Plan=p01
Default Exp/Contr=0.3,0.1
English Units
Geom File=g01
Flow File=f01
Plan File=p01
BEGIN DESCRIPTION:
Stream0155
END DESCRIPTION:

--- Stream0155.p01 (plan) ---

Plan Title=Multiple Run
Short Identifier=Multiple
Geom File=g01
Flow File=f01
Subcritical Flow
K Sum by GR= 0
Std Step Tol= 0.01
Critical Tol= 0.01
Num of Std Step Trials= 20
Max Error Tol= 0.3
Flow Tol Ratio= 0.001
Split Flow NTrial= 30
Split Flow Tol= 0.02
Split Flow Ratio= 0.02
Log Output Level= 0
Friction Slope Method= 1
Unsteady Friction Slope Method= 2
Unsteady Bridges Friction Slope Method= 1
Parabolic Critical Depth
Global Vel Dist=  1 , 1 , 1
Global Log Level= 0
CheckData=True
Encroach Param= -1, 0, 0, 0
BEGIN DESCRIPTION:
Multiple Run
END DESCRIPTION:

--- Stream0155.f01 (steady flow) ---

Flow Title=Multiple
Number of Profiles=7
Profile Names=10-year,25-year,50-year,1pct_min,100-year,1pct_plu,500-year
River Rch & RM= Stream0155,Reach-1,1132
     455     743    1006     662    1321    2636    2243
Boundary for River Rch & Prof#=Stream0155,Reach-1,1
Up Type=0
Dn Type=3
Dn Slope=0.005
Boundary for River Rch & Prof#=Stream0155,Reach-1,2
Up Type=0
Dn Type=3
Dn Slope=0.005
Boundary for River Rch & Prof#=Stream0155,Reach-1,3
Up Type=0
Dn Type=3
Dn Slope=0.005
Boundary for River Rch & Prof#=Stream0155,Reach-1,4
Up Type=0
Dn Type=3
Dn Slope=0.005
Boundary for River Rch & Prof#=Stream0155,Reach-1,5
Up Type=0
Dn Type=3
Dn Slope=0.005
Boundary for River Rch & Prof#=Stream0155,Reach-1,6
Up Type=0
Dn Type=3
Dn Slope=0.005
Boundary for River Rch & Prof#=Stream0155,Reach-1,7
Up Type=0
Dn Type=3
Dn Slope=0.005

--- Stream0155.g01 (geometry) ---

Geom Title=Existing Conditions

River Reach=Stream0155,Reach-1
Reach XY= 30
      1791978.57     13925566.30      1791992.71     13925566.65
      1792168.17     13925431.37      1792344.84     13925254.62
      1792365.32     13925235.78      1792372.71     13925230.86
      1792381.05     13925227.53      1792414.36     13925223.45
      1792423.35     13925221.02      1792431.05     13925216.84
      1792441.67     13925208.35      1792695.38     13924955.15
      1792711.37     13924938.18      1792719.15     13924927.24
      1792722.47     13924918.87      1792726.54     13924885.31
      1792728.97     13924876.17      1792730.84     13924872.16
      1792741.63     13924857.44      1792751.26     13924847.28
      1792761.26     13924838.30      1792771.34     13924832.48
      1792774.70     13924831.95      1792781.40     13924833.82
      1792791.44     13924841.09      1792818.76     13924866.25
      1792826.34     13924870.97      1792831.13     13924872.69
      1792849.63     13924875.13      1792875.00     13924875.00

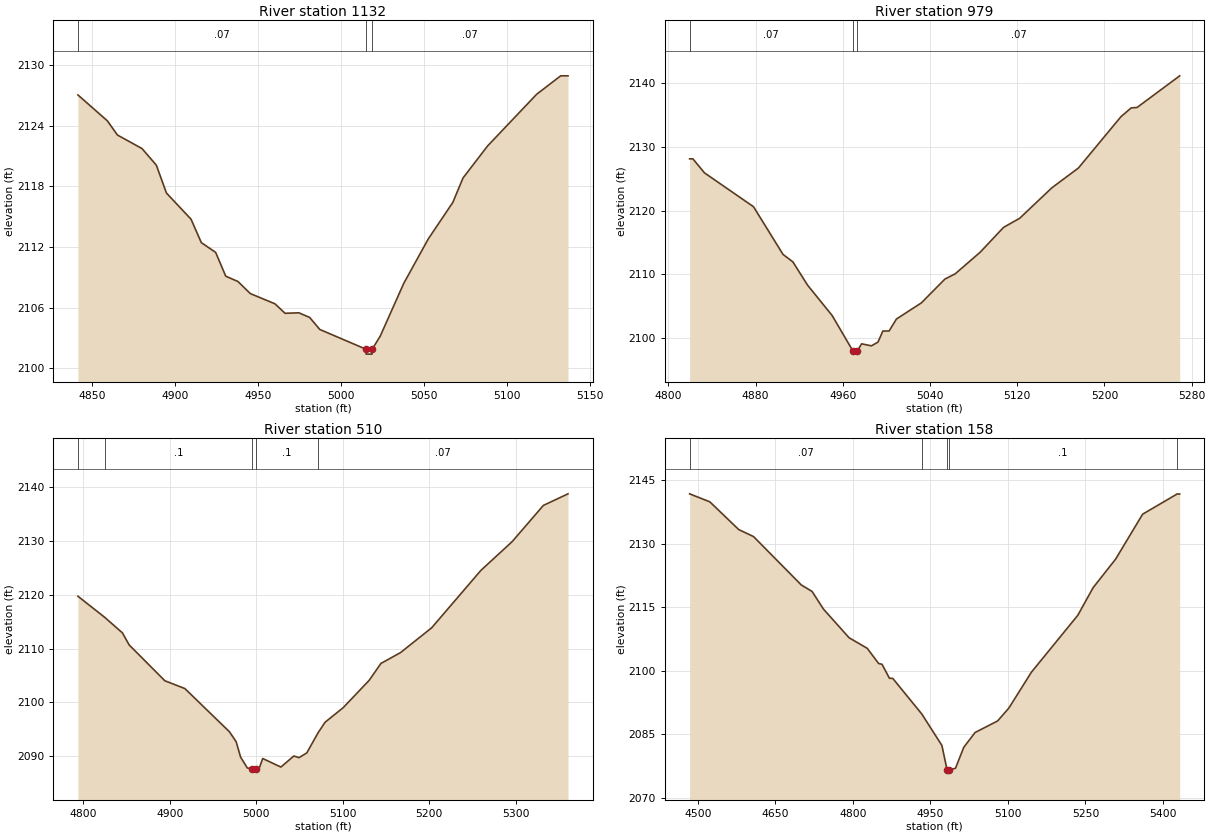
Type RM Length L Ch R = 1,1132,153,153,153
BEGIN DESCRIPTION:
Stream0155 5.0
END DESCRIPTION:
XS GIS Cut Line= 2
      1792183.61     13925610.76      1791942.76     13925440.43
#Sta/Elev= 30
  4841.5 2127.05  4859.2 2124.49  4865.3 2123.08  4880.1 2121.74  4888.7 2120.10
  4894.8 2117.34  4909.6 2114.75  4915.8 2112.43  4924.4 2111.47  4930.5 2109.11
  4937.8 2108.59  4945.3 2107.39  4960.1 2106.38  4966.2 2105.44  4974.5 2105.49
  4981.0 2105.03  4987.1 2103.84  5014.7 2101.90  5015.0 2101.40  5018.5 2101.40
  5018.7 2101.90  5023.5 2103.19  5037.6 2108.39  5052.4 2112.80  5067.2 2116.42
  5073.3 2118.83  5088.1 2122.00  5117.6 2127.11  5132.1 2128.94  5136.5 2128.94
#Mann=3,-1,0
  4841.5    0.07       0  5014.7    0.05       0  5018.7    0.07       0
Bank Sta=5014.7,5018.7
Exp/Cntr=0.3,0.1

Type RM Length L Ch R = 1,979,469,469,469
BEGIN DESCRIPTION:
Stream0155 2.0
END DESCRIPTION:
XS GIS Cut Line= 3
      1792275.02     13925575.03      1792175.00     13925425.00
      1791924.98     13925324.99
#Sta/Elev= 30
  4819.4 2128.14  4822.4 2128.14  4833.0 2125.94  4878.0 2120.62  4905.1 2113.12
  4914.1 2111.96  4927.6 2108.30  4950.1 2103.54  4969.2 2097.96  4969.4 2097.46
  4972.9 2097.46  4973.2 2097.96  4977.2 2099.08  4986.2 2098.76  4992.2 2099.35
  4996.7 2101.09  5002.4 2101.09  5009.1 2102.97  5032.0 2105.51  5053.6 2109.25
  5063.0 2110.07  5085.9 2113.46  5107.4 2117.37  5122.2 2118.80  5151.8 2123.60
  5176.1 2126.70  5215.1 2134.76  5224.5 2136.14  5229.9 2136.21  5269.0 2141.18
#Mann=3,-1,0
  4819.4    0.07       0  4969.2    0.05       0  4973.2    0.07       0
Bank Sta=4969.2,4973.2
Exp/Cntr=0.3,0.1

Type RM Length L Ch R = 1,510,352,352,352
BEGIN DESCRIPTION:
Stream0155 1.0
END DESCRIPTION:
XS GIS Cut Line= 3
      1792575.00     13925324.99      1792525.00     13925125.00
      1792225.00     13924925.00
#Sta/Elev= 30
  4793.9 2119.69  4824.8 2115.79  4845.4 2112.89  4853.2 2110.66  4894.4 2104.03
  4917.6 2102.58  4969.1 2094.58  4976.9 2092.73  4982.0 2089.89  4989.7 2087.89
  4995.5 2087.60  4995.7 2087.10  4999.5 2087.60  5003.0 2087.60  5007.6 2089.62
  5028.6 2088.04  5043.6 2090.09  5049.6 2089.78  5058.6 2090.67  5071.6 2094.39
  5079.7 2096.34  5100.7 2099.05  5130.7 2104.11  5144.3 2107.24  5166.8 2109.23
  5202.9 2113.83  5259.9 2124.48  5296.0 2129.80  5332.1 2136.51  5360.6 2138.66
#Mann=5,-1,0
  4793.9    0.07       0  4824.8     0.1       0  4995.5    0.05       0
  4999.5     0.1       0  5071.6    0.07       0
Bank Sta=4995.5,4999.5
Exp/Cntr=0.3,0.1

Type RM Length L Ch R = 1,158,0,0,0
BEGIN DESCRIPTION:
Stream0155 0.0
END DESCRIPTION:
XS GIS Cut Line= 3
      1793078.16     13925246.30      1792765.65     13924871.29
      1792362.10     13924649.99
#Sta/Elev= 30
  4484.0 2141.78  4523.1 2139.89  4579.1 2133.33  4607.7 2131.68  4700.1 2120.25
  4721.0 2118.71  4743.1 2114.53  4792.6 2107.77  4827.7 2105.28  4849.8 2101.68
  4856.3 2101.51  4870.7 2098.20  4877.2 2098.16  4933.4 2089.74  4972.2 2082.33
  4982.3 2076.52  4982.5 2076.02  4986.3 2076.52  4998.5 2076.93  5014.6 2081.90
  5036.4 2085.38  5080.0 2088.11  5101.8 2091.16  5145.4 2099.63  5235.2 2113.08
  5264.9 2119.61  5308.5 2126.37  5360.7 2136.97  5427.7 2141.76  5432.4 2141.72
#Mann=5,-1,0
  4484.0    0.07       0  4933.4     0.1       0  4982.3    0.05       0
  4986.3     0.1       0  5427.7    0.07       0
Bank Sta=4982.3,4986.3
Exp/Cntr=0.3,0.1

Chan Stop Cuts=-1