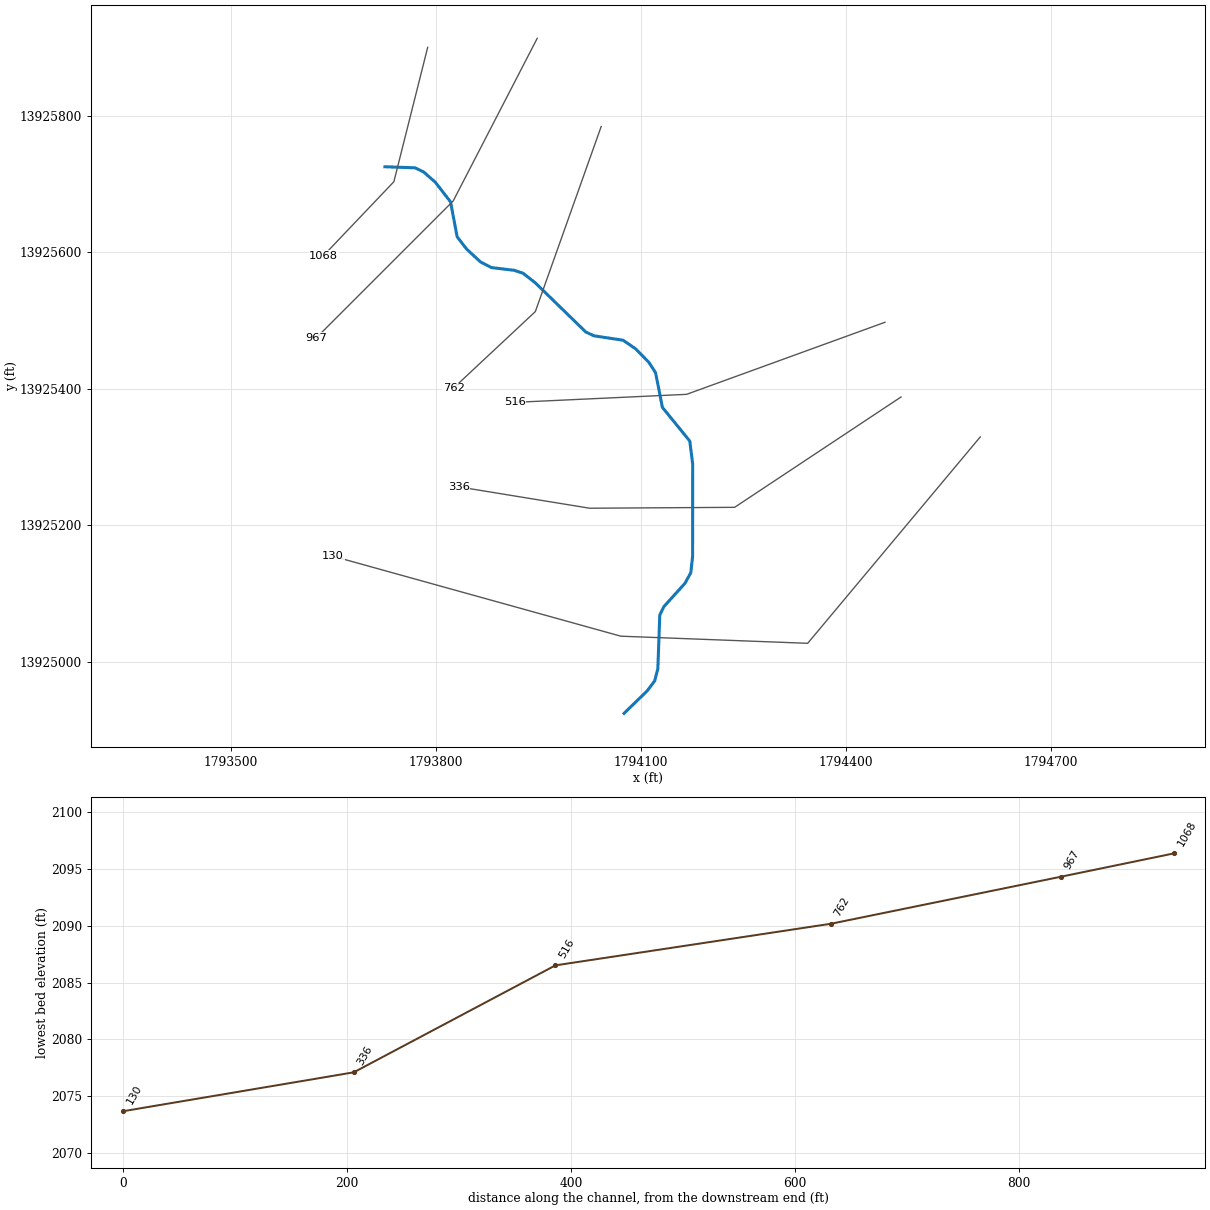
--- Stream0156.prj (project) ---

Proj Title=Stream0156 Base Level Engineering
Current Plan=p01
Default Exp/Contr=0.3,0.1
English Units
Geom File=g01
Flow File=f01
Plan File=p01
BEGIN DESCRIPTION:
Stream0156
END DESCRIPTION:

--- Stream0156.p01 (plan) ---

Plan Title=Multiple Run
Short Identifier=Multiple
Geom File=g01
Flow File=f01
Subcritical Flow
K Sum by GR= 0
Std Step Tol= 0.01
Critical Tol= 0.01
Num of Std Step Trials= 20
Max Error Tol= 0.3
Flow Tol Ratio= 0.001
Split Flow NTrial= 30
Split Flow Tol= 0.02
Split Flow Ratio= 0.02
Log Output Level= 0
Friction Slope Method= 1
Unsteady Friction Slope Method= 2
Unsteady Bridges Friction Slope Method= 1
Parabolic Critical Depth
Global Vel Dist=  1 , 1 , 1
Global Log Level= 0
CheckData=True
Encroach Param= -1, 0, 0, 0
BEGIN DESCRIPTION:
Multiple Run
END DESCRIPTION:

--- Stream0156.f01 (steady flow) ---

Flow Title=Multiple
Number of Profiles=7
Profile Names=10-year,25-year,50-year,1pct_min,100-year,1pct_plu,500-year
River Rch & RM= Stream0156,Reach-1,1068
     365     586     785     511    1019    2033    1690
Boundary for River Rch & Prof#=Stream0156,Reach-1,1
Up Type=0
Dn Type=3
Dn Slope=0.005
Boundary for River Rch & Prof#=Stream0156,Reach-1,2
Up Type=0
Dn Type=3
Dn Slope=0.005
Boundary for River Rch & Prof#=Stream0156,Reach-1,3
Up Type=0
Dn Type=3
Dn Slope=0.005
Boundary for River Rch & Prof#=Stream0156,Reach-1,4
Up Type=0
Dn Type=3
Dn Slope=0.005
Boundary for River Rch & Prof#=Stream0156,Reach-1,5
Up Type=0
Dn Type=3
Dn Slope=0.005
Boundary for River Rch & Prof#=Stream0156,Reach-1,6
Up Type=0
Dn Type=3
Dn Slope=0.005
Boundary for River Rch & Prof#=Stream0156,Reach-1,7
Up Type=0
Dn Type=3
Dn Slope=0.005

--- Stream0156.g01 (geometry) ---

Geom Title=Existing Conditions

River Reach=Stream0156,Reach-1
Reach XY= 30
      1793725.00     13925725.00      1793769.13     13925723.44
      1793781.63     13925717.41      1793798.98     13925702.17
      1793821.13     13925673.50      1793830.74     13925622.47
      1793844.63     13925604.53      1793865.00     13925585.65
      1793880.87     13925577.46      1793914.31     13925573.43
      1793927.26     13925569.12      1793945.06     13925555.17
      1794018.98     13925483.18      1794031.09     13925477.56
      1794073.57     13925471.11      1794092.05     13925458.51
      1794111.53     13925438.57      1794121.14     13925423.58
      1794131.15     13925372.85      1794171.25     13925323.45
      1794175.44     13925290.18      1794175.36     13925154.85
      1794172.74     13925130.94      1794164.15     13925115.35
      1794133.18     13925081.04      1794127.32     13925069.04
      1794124.47     13924990.22      1794119.78     13924972.45
      1794108.88     13924957.95      1794075.00     13924925.00

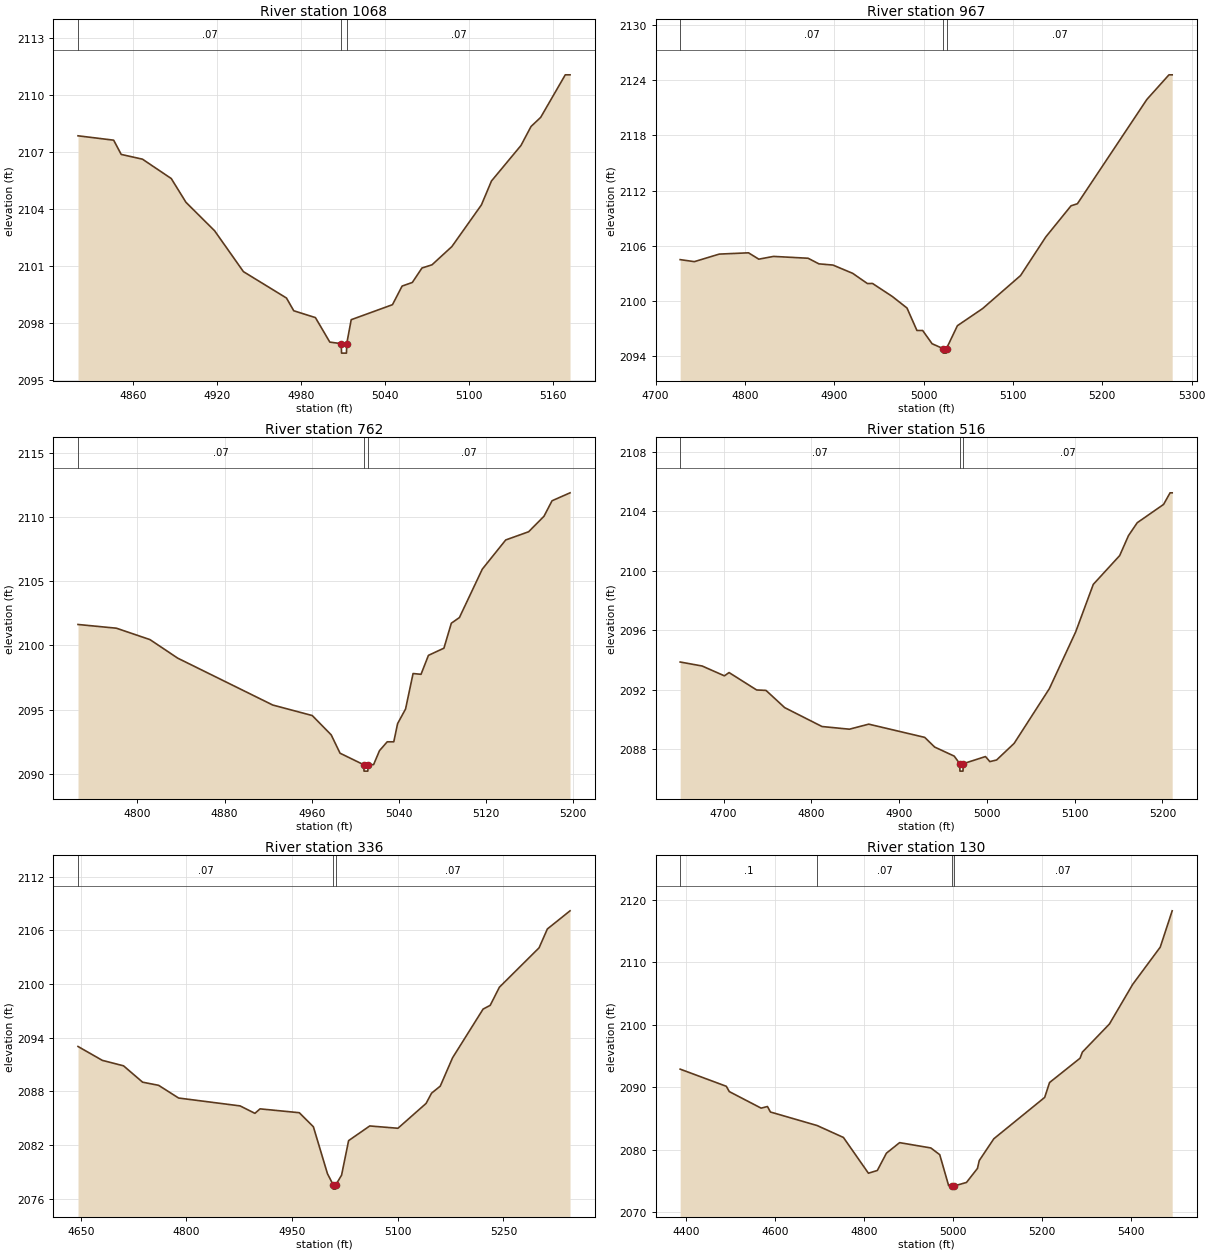
Type RM Length L Ch R = 1,1068,101,101,101
BEGIN DESCRIPTION:
Stream0156 3.0
END DESCRIPTION:
XS GIS Cut Line= 3
      1793787.62     13925899.70      1793738.15     13925703.12
      1793635.29     13925595.05
#Sta/Elev= 30
  4820.4 2107.83  4845.9 2107.60  4851.3 2106.85  4866.5 2106.60  4887.1 2105.58
  4897.6 2104.33  4918.1 2102.83  4938.7 2100.68  4969.5 2099.29  4974.7 2098.62
  4990.2 2098.26  5000.5 2096.97  5008.6 2096.89  5008.9 2096.39  5012.4 2096.39
  5012.6 2096.89  5015.8 2098.15  5045.3 2098.94  5052.2 2099.92  5059.5 2100.11
  5066.4 2100.87  5073.6 2101.04  5087.8 2102.00  5108.9 2104.19  5116.1 2105.45
  5137.2 2107.32  5144.4 2108.32  5151.3 2108.80  5168.9 2111.04  5172.3 2111.04
#Mann=3,-1,0
  4820.4    0.07       0  5008.6    0.05       0  5012.6    0.07       0
Bank Sta=5008.6,5012.6
Exp/Cntr=0.3,0.1

Type RM Length L Ch R = 1,967,205,205,205
BEGIN DESCRIPTION:
Stream0156 2.0
END DESCRIPTION:
XS GIS Cut Line= 3
      1793947.93     13925912.95      1793825.00     13925675.00
      1793624.98     13925474.98
#Sta/Elev= 30
  4727.5 2104.49  4743.4 2104.27  4771.2 2105.09  4804.0 2105.23  4815.5 2104.54
  4832.0 2104.84  4870.7 2104.64  4882.8 2104.03  4898.5 2103.90  4920.6 2103.00
  4937.1 2101.89  4942.8 2101.90  4964.9 2100.49  4981.4 2099.23  4992.5 2096.79
  4998.9 2096.79  5009.5 2095.35  5021.6 2094.83  5021.9 2094.33  5025.4 2094.33
  5025.6 2094.83  5037.8 2097.31  5066.0 2099.17  5108.5 2102.76  5136.7 2106.95
  5165.0 2110.34  5172.1 2110.56  5249.9 2121.90  5274.6 2124.57  5278.2 2124.57
#Mann=3,-1,0
  4727.5    0.07       0  5021.6    0.05       0  5025.6    0.07       0
Bank Sta=5021.6,5025.6
Exp/Cntr=0.3,0.1

Type RM Length L Ch R = 1,762,246,246,246
BEGIN DESCRIPTION:
Stream0156 2.5
END DESCRIPTION:
XS GIS Cut Line= 3
      1794041.53     13925783.84      1793945.18     13925513.02
      1793825.41     13925401.06
#Sta/Elev= 30
  4745.6 2101.64  4780.8 2101.35  4811.6 2100.46  4837.1 2099.01  4924.3 2095.35
  4960.5 2094.53  4977.9 2093.02  4986.0 2091.59  5007.7 2090.69  5008.0 2090.19
  5011.5 2090.19  5011.7 2090.69  5016.8 2090.70  5022.2 2091.79  5029.3 2092.48
  5035.3 2092.48  5038.8 2093.90  5046.1 2095.04  5053.0 2097.81  5060.3 2097.75
  5067.1 2099.23  5081.3 2099.79  5088.1 2101.74  5095.5 2102.18  5116.5 2105.96
  5138.0 2108.24  5159.0 2108.88  5173.1 2110.09  5180.5 2111.30  5197.0 2111.92
#Mann=3,-1,0
  4745.6    0.07       0  5007.7    0.05       0  5011.7    0.07       0
Bank Sta=5007.7,5011.7
Exp/Cntr=0.3,0.1

Type RM Length L Ch R = 1,516,180,180,180
BEGIN DESCRIPTION:
Stream0156 0.6
END DESCRIPTION:
XS GIS Cut Line= 3
      1794456.90     13925497.39      1794166.53     13925391.92
      1793915.23     13925380.20
#Sta/Elev= 30
  4650.6 2093.86  4675.7 2093.59  4701.0 2092.93  4706.3 2093.15  4737.7 2091.98
  4748.4 2091.95  4769.7 2090.79  4812.2 2089.52  4843.4 2089.34  4865.4 2089.68
  4929.2 2088.79  4940.5 2088.14  4962.8 2087.53  4969.1 2087.02  4969.3 2086.52
  4972.8 2086.52  4973.1 2087.02  4998.4 2087.50  5003.4 2087.16  5011.1 2087.27
  5031.1 2088.39  5071.2 2092.07  5101.2 2095.89  5121.2 2099.08  5151.3 2101.02
  5161.3 2102.36  5171.3 2103.23  5201.3 2104.46  5208.7 2105.24  5211.1 2105.24
#Mann=3,-1,0
  4650.6    0.07       0  4969.1    0.05       0  4973.1    0.07       0
Bank Sta=4969.1,4973.1
Exp/Cntr=0.3,0.1

Type RM Length L Ch R = 1,336,206,206,206
BEGIN DESCRIPTION:
Stream0156 0.5
END DESCRIPTION:
XS GIS Cut Line= 4
      1794480.38     13925388.04      1794236.85     13925226.56
      1794024.61     13925225.25      1793833.19     13925256.51
#Sta/Elev= 30
  4646.1 2093.03  4680.6 2091.48  4710.7 2090.87  4737.8 2089.04  4760.5 2088.69
  4788.9 2087.27  4876.2 2086.39  4897.2 2085.56  4904.5 2086.06  4960.2 2085.63
  4980.2 2084.06  5000.2 2078.81  5008.2 2077.59  5008.4 2077.09  5011.9 2077.09
  5012.2 2077.59  5020.2 2078.65  5030.2 2082.51  5060.2 2084.15  5100.2 2083.89
  5140.2 2086.67  5147.9 2087.81  5160.3 2088.60  5177.7 2091.76  5221.1 2097.21
  5231.2 2097.63  5244.2 2099.65  5300.6 2104.06  5312.3 2106.16  5344.5 2108.19
#Mann=3,-1,0
  4646.1    0.07       0  5008.2    0.05       0  5012.2    0.07       0
Bank Sta=5008.2,5012.2
Exp/Cntr=0.3,0.1

Type RM Length L Ch R = 1,130,0,0,0
BEGIN DESCRIPTION:
Stream0156 0.0
END DESCRIPTION:
XS GIS Cut Line= 4
      1794596.38     13925329.63      1794343.77     13925027.54
      1794070.33     13925037.96      1793649.21     13925154.94
#Sta/Elev= 30
  4387.1 2092.89  4490.7 2090.14  4497.4 2089.29  4568.8 2086.64  4583.1 2086.90
  4589.7 2086.02  4694.6 2083.85  4753.6 2081.94  4809.7 2076.21  4829.7 2076.65
  4850.1 2079.42  4879.7 2081.11  4949.8 2080.26  4969.8 2079.18  4989.8 2074.22
  4997.8 2074.16  4998.1 2073.66  5001.8 2074.16  5029.8 2074.73  5054.5 2076.98
  5058.5 2078.24  5091.2 2081.73  5205.4 2088.36  5216.3 2090.74  5284.8 2094.64
  5290.0 2095.62  5350.7 2100.12  5403.1 2106.49  5464.8 2112.44  5491.6 2118.26
#Mann=4,-1,0
  4387.1     0.1       0  4694.6    0.07       0  4997.8    0.05       0
  5001.8    0.07       0
Bank Sta=4997.8,5001.8
Exp/Cntr=0.3,0.1

Chan Stop Cuts=-1