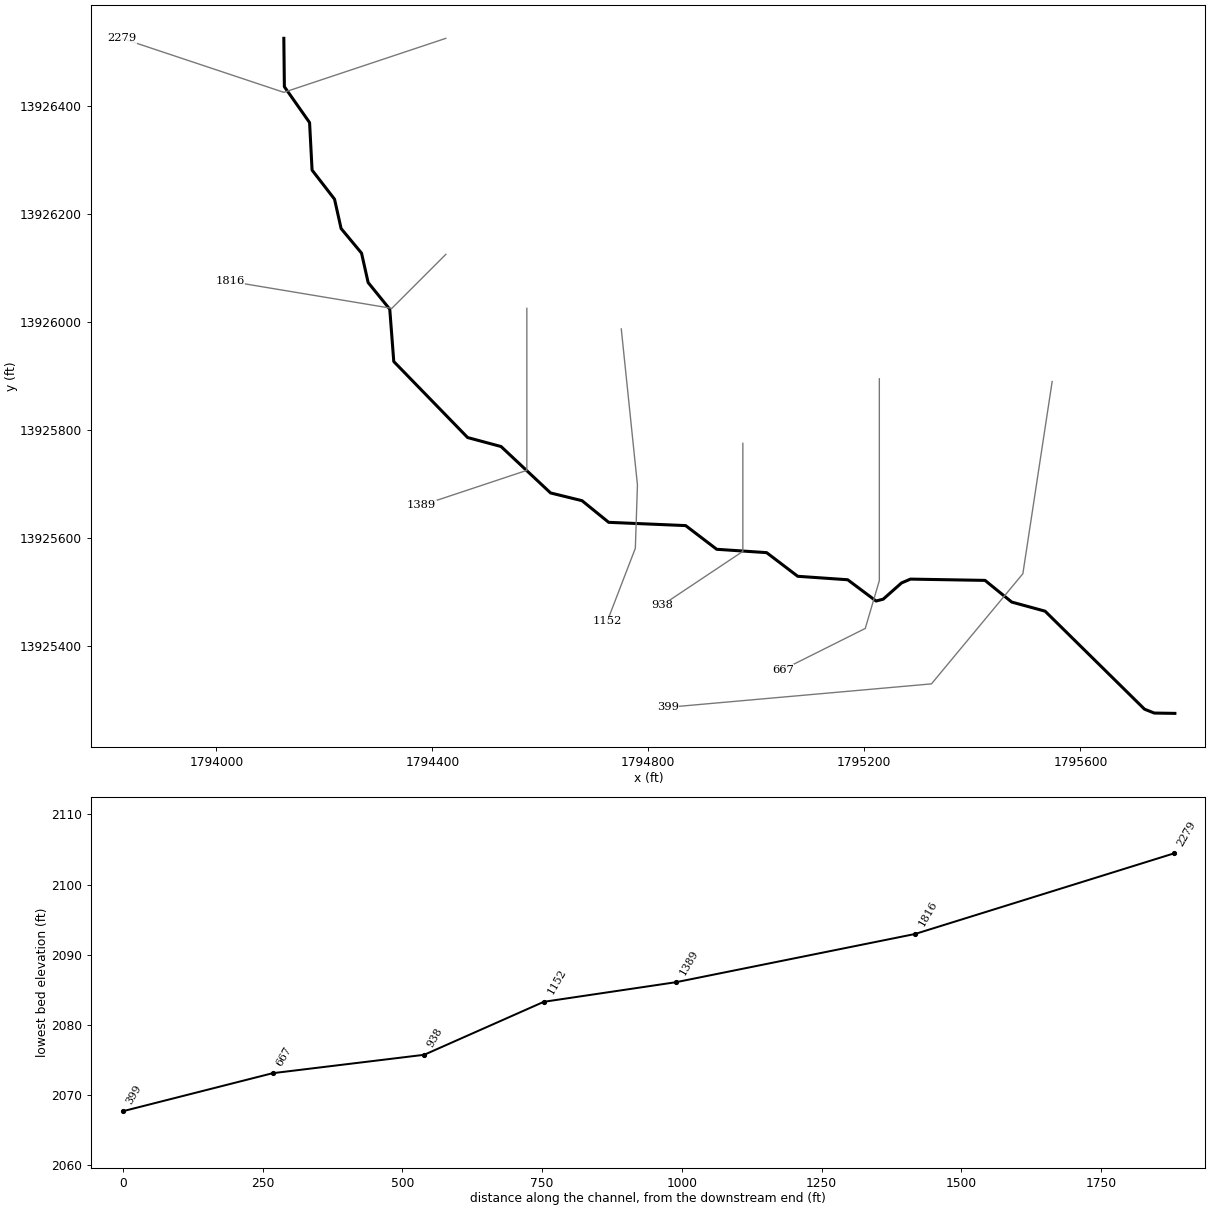
--- Stream0157.prj (project) ---

Proj Title=Stream0157 Base Level Engineering
Current Plan=p01
Default Exp/Contr=0.3,0.1
English Units
Geom File=g01
Flow File=f01
Plan File=p01
BEGIN DESCRIPTION:
Stream0157
END DESCRIPTION:

--- Stream0157.p01 (plan) ---

Plan Title=Multiple Run
Short Identifier=Multiple
Geom File=g01
Flow File=f01
Subcritical Flow
K Sum by GR= 0
Std Step Tol= 0.01
Critical Tol= 0.01
Num of Std Step Trials= 20
Max Error Tol= 0.3
Flow Tol Ratio= 0.001
Split Flow NTrial= 30
Split Flow Tol= 0.02
Split Flow Ratio= 0.02
Log Output Level= 0
Friction Slope Method= 1
Unsteady Friction Slope Method= 2
Unsteady Bridges Friction Slope Method= 1
Parabolic Critical Depth
Global Vel Dist=  1 , 1 , 1
Global Log Level= 0
CheckData=True
Encroach Param= -1, 0, 0, 0
BEGIN DESCRIPTION:
Multiple Run
END DESCRIPTION:

--- Stream0157.f01 (steady flow) ---

Flow Title=Multiple
Number of Profiles=7
Profile Names=10-year,25-year,50-year,1pct_min,100-year,1pct_plu,500-year
River Rch & RM= Stream0157,Reach-1,2279
     330     523     694     448     893    1782    1456
Boundary for River Rch & Prof#=Stream0157,Reach-1,1
Up Type=0
Dn Type=3
Dn Slope=0.005
Boundary for River Rch & Prof#=Stream0157,Reach-1,2
Up Type=0
Dn Type=3
Dn Slope=0.005
Boundary for River Rch & Prof#=Stream0157,Reach-1,3
Up Type=0
Dn Type=3
Dn Slope=0.005
Boundary for River Rch & Prof#=Stream0157,Reach-1,4
Up Type=0
Dn Type=3
Dn Slope=0.005
Boundary for River Rch & Prof#=Stream0157,Reach-1,5
Up Type=0
Dn Type=3
Dn Slope=0.005
Boundary for River Rch & Prof#=Stream0157,Reach-1,6
Up Type=0
Dn Type=3
Dn Slope=0.005
Boundary for River Rch & Prof#=Stream0157,Reach-1,7
Up Type=0
Dn Type=3
Dn Slope=0.005

--- Stream0157.g01 (geometry) ---

Geom Title=Existing Conditions

River Reach=Stream0157,Reach-1
Reach XY= 30
      1794125.00     13926525.00      1794126.02     13926435.42
      1794172.67     13926369.03      1794177.33     13926280.97
      1794218.88     13926227.18      1794231.08     13926172.80
      1794268.92     13926127.20      1794281.12     13926072.82
      1794321.17     13926023.41      1794328.61     13925926.50
      1794465.32     13925785.78      1794527.28     13925769.13
      1794618.95     13925683.16      1794677.17     13925668.86
      1794726.56     13925628.76      1794869.06     13925622.73
      1794926.60     13925578.86      1795019.03     13925572.65
      1795076.60     13925528.85      1795169.11     13925522.45
      1795221.70     13925483.08      1795234.90     13925486.47
      1795268.82     13925516.55      1795285.44     13925523.63
      1795423.44     13925521.26      1795472.83     13925481.14
      1795534.68     13925464.24      1795718.79     13925282.76
      1795736.84     13925275.59      1795775.00     13925275.00

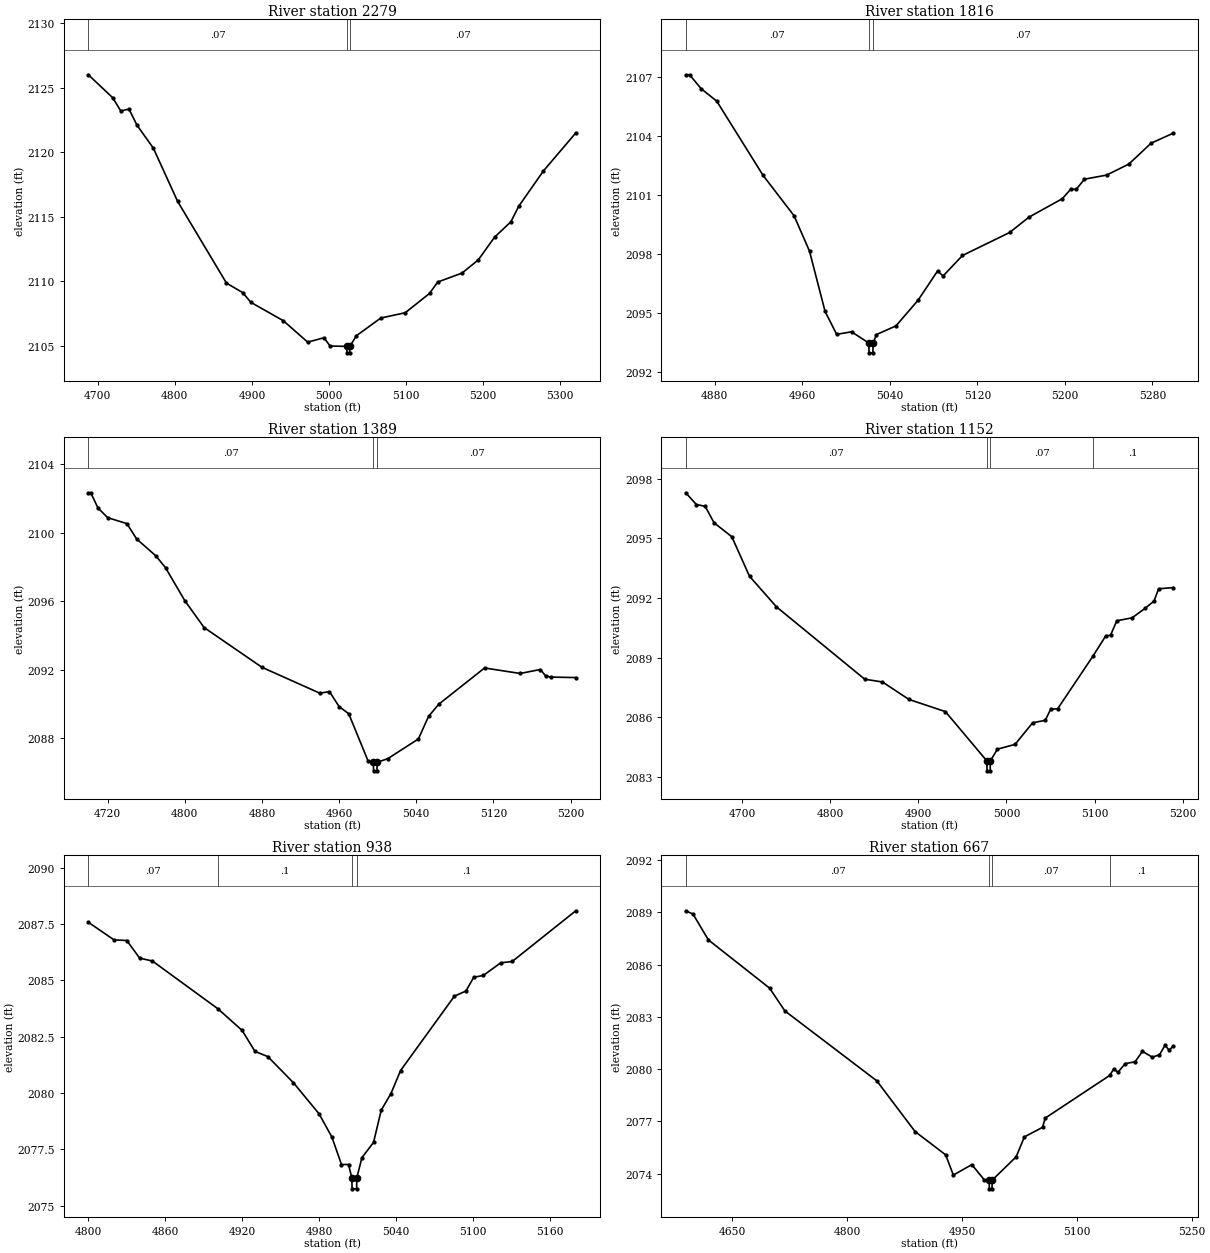
Type RM Length L Ch R = 1,2279,463,463,463
BEGIN DESCRIPTION:
Stream0157 4.0
END DESCRIPTION:
XS GIS Cut Line= 3
      1794424.97     13926524.99      1794125.00     13926425.00
      1793825.03     13926524.99
#Sta/Elev= 30
  4687.8 2126.01  4719.4 2124.23  4729.9 2123.20  4740.5 2123.35  4751.0 2122.09
  4772.1 2120.32  4803.7 2116.18  4867.0 2109.85  4888.1 2109.11  4898.6 2108.36
  4940.8 2106.93  4972.4 2105.27  4993.5 2105.61  5001.4 2104.97  5023.1 2104.94
  5023.3 2104.44  5026.8 2104.44  5027.1 2104.94  5035.6 2105.77  5067.2 2107.14
  5098.9 2107.55  5130.5 2109.05  5141.0 2109.93  5172.7 2110.63  5193.7 2111.65
  5214.8 2113.41  5235.9 2114.60  5246.4 2115.83  5278.1 2118.54  5320.2 2121.50
#Mann=3,-1,0
  4687.8    0.07       0  5023.1    0.05       0  5027.1    0.07       0
Bank Sta=5023.1,5027.1
Exp/Cntr=0.3,0.1

Type RM Length L Ch R = 1,1816,427,427,427
BEGIN DESCRIPTION:
Stream0157 3.0
END DESCRIPTION:
XS GIS Cut Line= 3
      1794424.98     13926124.98      1794325.00     13926025.00
      1794025.03     13926074.99
#Sta/Elev= 30
  4853.5 2107.10  4857.0 2107.10  4867.6 2106.39  4881.8 2105.76  4924.2 2101.98
  4952.5 2099.93  4966.6 2098.13  4980.8 2095.07  4991.4 2093.90  5005.0 2094.03
  5020.8 2093.46  5021.0 2092.96  5024.5 2092.96  5024.8 2093.46  5027.8 2093.89
  5045.6 2094.33  5065.9 2095.64  5083.6 2097.12  5088.7 2096.87  5106.4 2097.91
  5149.5 2099.08  5167.2 2099.86  5197.7 2100.80  5205.3 2101.28  5210.3 2101.27
  5217.9 2101.79  5238.2 2102.00  5258.5 2102.56  5278.8 2103.62  5299.0 2104.13
#Mann=3,-1,0
  4853.5    0.07       0  5020.8    0.05       0  5024.8    0.07       0
Bank Sta=5020.8,5024.8
Exp/Cntr=0.3,0.1

Type RM Length L Ch R = 1,1389,237,237,237
BEGIN DESCRIPTION:
Stream0157 2.0
END DESCRIPTION:
XS GIS Cut Line= 3
      1794575.00     13926025.00      1794575.00     13925725.00
      1794380.10     13925660.16
#Sta/Elev= 30
  4700.0 2102.32  4702.5 2102.32  4710.0 2101.43  4720.0 2100.87  4740.0 2100.52
  4750.0 2099.63  4770.0 2098.64  4780.0 2097.95  4800.0 2096.03  4820.0 2094.46
  4880.0 2092.14  4940.0 2090.63  4950.0 2090.72  4960.0 2089.85  4970.0 2089.43
  4990.0 2086.68  4995.5 2086.60  4995.7 2086.10  4999.2 2086.10  4999.5 2086.60
  5010.5 2086.81  5042.2 2087.96  5052.7 2089.27  5063.2 2089.98  5110.8 2092.10
  5147.7 2091.78  5168.6 2092.01  5174.1 2091.64  5179.3 2091.57  5205.4 2091.54
#Mann=3,-1,0
  4700.0    0.07       0  4995.5    0.05       0  4999.5    0.07       0
Bank Sta=4995.5,4999.5
Exp/Cntr=0.3,0.1

Type RM Length L Ch R = 1,1152,214,214,214
BEGIN DESCRIPTION:
Stream0157 1.1
END DESCRIPTION:
XS GIS Cut Line= 4
      1794749.87     13925986.93      1794779.82     13925697.91
      1794775.91     13925580.72      1794723.83     13925445.31
#Sta/Elev= 30
  4636.2 2097.29  4648.2 2096.70  4658.2 2096.61  4668.3 2095.78  4688.4 2095.08
  4708.5 2093.09  4739.1 2091.55  4839.2 2087.91  4859.3 2087.77  4889.5 2086.89
  4930.7 2086.28  4977.7 2083.80  4978.0 2083.30  4981.5 2083.30  4981.7 2083.80
  4989.7 2084.39  5009.7 2084.63  5029.7 2085.72  5044.0 2085.84  5050.1 2086.40
  5058.0 2086.42  5098.2 2089.08  5112.6 2090.09  5118.0 2090.12  5125.1 2090.85
  5142.6 2091.00  5157.3 2091.48  5167.3 2091.84  5172.6 2092.46  5189.1 2092.52
#Mann=4,-1,0
  4636.2    0.07       0  4977.7    0.05       0  4981.7    0.07       0
  5098.2     0.1       0
Bank Sta=4977.7,4981.7
Exp/Cntr=0.3,0.1

Type RM Length L Ch R = 1,938,271,271,271
BEGIN DESCRIPTION:
Stream0157 1.0
END DESCRIPTION:
XS GIS Cut Line= 3
      1794975.00     13925775.00      1794975.00     13925575.00
      1794824.98     13925474.99
#Sta/Elev= 30
  4800.0 2087.58  4820.0 2086.80  4830.0 2086.77  4840.0 2085.99  4850.0 2085.86
  4901.1 2083.74  4920.0 2082.78  4930.0 2081.85  4940.0 2081.62  4960.0 2080.46
  4980.0 2079.08  4990.0 2078.05  4997.5 2076.83  5003.0 2076.83  5005.5 2076.25
  5005.8 2075.75  5009.3 2075.75  5009.5 2076.25  5013.5 2077.14  5022.5 2077.81
  5028.5 2079.24  5036.1 2079.98  5043.6 2081.00  5085.6 2084.30  5094.6 2084.53
  5100.7 2085.14  5108.2 2085.22  5121.7 2085.78  5130.7 2085.84  5180.3 2088.09
#Mann=4,-1,0
  4800.0    0.07       0  4901.1     0.1       0  5005.5    0.05       0
  5009.5     0.1       0
Bank Sta=5005.5,5009.5
Exp/Cntr=0.3,0.1

Type RM Length L Ch R = 1,667,268,268,268
BEGIN DESCRIPTION:
Stream0157 0.3
END DESCRIPTION:
XS GIS Cut Line= 4
      1795227.73     13925894.55      1795227.73     13925520.83
      1795201.69     13925432.29      1795049.02     13925355.95
#Sta/Elev= 30
  4589.1 2089.09  4598.6 2088.90  4618.6 2087.42  4698.6 2084.65  4718.6 2083.34
  4838.6 2079.33  4888.6 2076.42  4928.6 2075.08  4938.6 2073.92  4962.8 2074.52
  4979.3 2073.63  4985.4 2073.63  4985.6 2073.13  4989.1 2073.13  4989.4 2073.63
  5020.7 2074.97  5031.4 2076.11  5055.1 2076.66  5058.6 2077.19  5142.9 2079.64
  5148.1 2080.01  5153.6 2079.82  5163.2 2080.32  5176.0 2080.42  5185.6 2081.02
  5198.4 2080.69  5207.9 2080.82  5215.1 2081.37  5220.7 2081.08  5225.8 2081.34
#Mann=4,-1,0
  4589.1    0.07       0  4985.4    0.05       0  4989.4    0.07       0
  5142.9     0.1       0
Bank Sta=4985.4,4989.4
Exp/Cntr=0.3,0.1

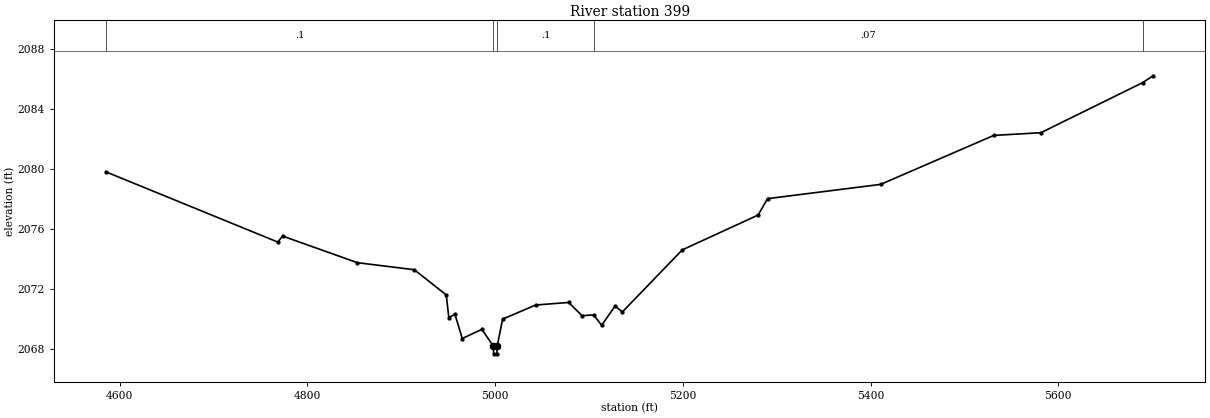
Type RM Length L Ch R = 1,399,0,0,0
BEGIN DESCRIPTION:
Stream0157 0.0
END DESCRIPTION:
XS GIS Cut Line= 4
      1795547.76     13925889.51      1795493.51     13925533.62
      1795324.24     13925329.62      1794835.95     13925286.22
#Sta/Elev= 30
  4585.7 2079.82  4768.6 2075.15  4773.7 2075.55  4853.3 2073.78  4914.0 2073.31
  4948.1 2071.63  4950.8 2070.12  4957.3 2070.35  4965.1 2068.73  4986.0 2069.34
  4998.3 2068.21  4998.5 2067.71  5002.0 2067.71  5002.3 2068.21  5008.1 2070.02
  5043.3 2070.96  5078.4 2071.13  5092.7 2070.25  5105.1 2070.30  5113.6 2069.61
  5127.9 2070.89  5135.7 2070.50  5199.5 2074.63  5280.3 2076.95  5290.3 2078.04
  5410.8 2078.99  5531.3 2082.25  5581.5 2082.43  5689.8 2085.76  5701.0 2086.22
#Mann=5,-1,0
  4585.7     0.1       0  4998.3    0.05       0  5002.3     0.1       0
  5105.1    0.07       0  5689.8     0.1       0
Bank Sta=4998.3,5002.3
Exp/Cntr=0.3,0.1

Chan Stop Cuts=-1