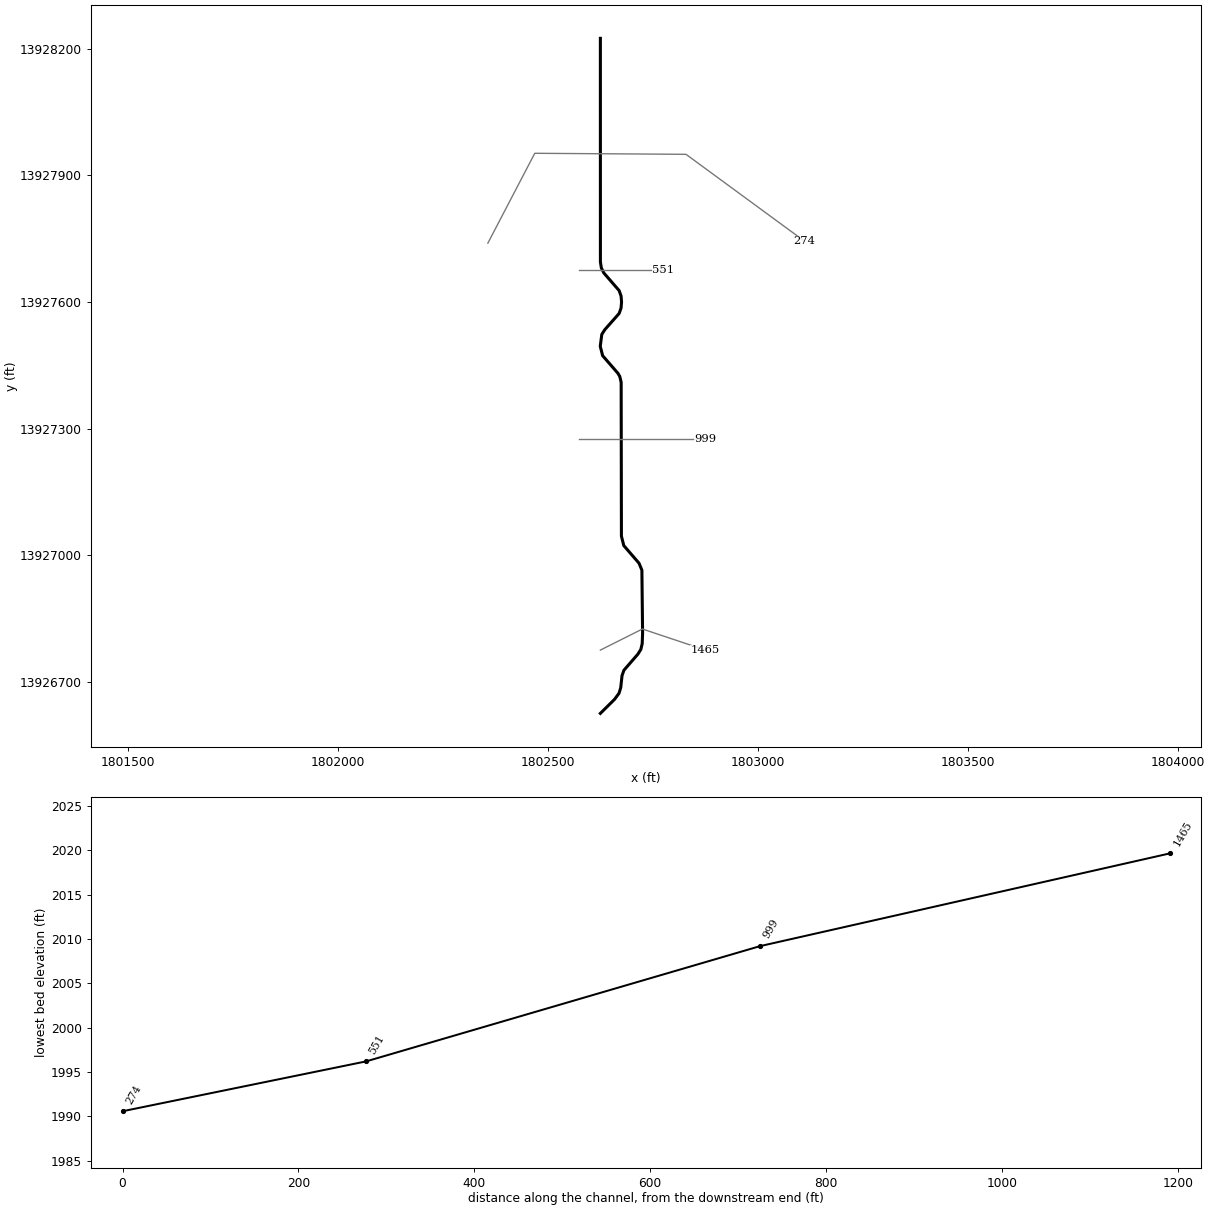
--- Stream0158.prj (project) ---

Proj Title=Stream0158 Base Level Engineering
Current Plan=p01
Default Exp/Contr=0.3,0.1
English Units
Geom File=g01
Flow File=f01
Plan File=p01
BEGIN DESCRIPTION:
Stream0158
END DESCRIPTION:

--- Stream0158.p01 (plan) ---

Plan Title=Multiple Run
Short Identifier=Multiple
Geom File=g01
Flow File=f01
Subcritical Flow
K Sum by GR= 0
Std Step Tol= 0.01
Critical Tol= 0.01
Num of Std Step Trials= 20
Max Error Tol= 0.3
Flow Tol Ratio= 0.001
Split Flow NTrial= 30
Split Flow Tol= 0.02
Split Flow Ratio= 0.02
Log Output Level= 0
Friction Slope Method= 1
Unsteady Friction Slope Method= 2
Unsteady Bridges Friction Slope Method= 1
Parabolic Critical Depth
Global Vel Dist=  1 , 1 , 1
Global Log Level= 0
CheckData=True
Encroach Param= -1, 0, 0, 0
BEGIN DESCRIPTION:
Multiple Run
END DESCRIPTION:

--- Stream0158.f01 (steady flow) ---

Flow Title=Multiple
Number of Profiles=7
Profile Names=10-year,25-year,50-year,1pct_min,100-year,1pct_plu,500-year
River Rch & RM= Stream0158,Reach-1,1465
     471     772    1047     690    1376    2745    2342
Boundary for River Rch & Prof#=Stream0158,Reach-1,1
Up Type=0
Dn Type=3
Dn Slope=0.005
Boundary for River Rch & Prof#=Stream0158,Reach-1,2
Up Type=0
Dn Type=3
Dn Slope=0.005
Boundary for River Rch & Prof#=Stream0158,Reach-1,3
Up Type=0
Dn Type=3
Dn Slope=0.005
Boundary for River Rch & Prof#=Stream0158,Reach-1,4
Up Type=0
Dn Type=3
Dn Slope=0.005
Boundary for River Rch & Prof#=Stream0158,Reach-1,5
Up Type=0
Dn Type=3
Dn Slope=0.005
Boundary for River Rch & Prof#=Stream0158,Reach-1,6
Up Type=0
Dn Type=3
Dn Slope=0.005
Boundary for River Rch & Prof#=Stream0158,Reach-1,7
Up Type=0
Dn Type=3
Dn Slope=0.005

--- Stream0158.g01 (geometry) ---

Geom Title=Existing Conditions

River Reach=Stream0158,Reach-1
Reach XY= 30
      1802625.00     13926625.00      1802658.59     13926658.07
      1802669.33     13926672.63      1802673.41     13926685.66
      1802676.52     13926714.37      1802681.03     13926727.22
      1802714.22     13926765.32      1802721.26     13926776.55
      1802724.50     13926790.21      1802725.46     13926814.81
      1802723.78     13926964.49      1802716.86     13926981.06
      1802680.75     13927022.67      1802675.07     13927045.03
      1802674.46     13927409.79      1802671.19     13927423.45
      1802666.81     13927431.08      1802630.38     13927472.82
      1802624.72     13927495.18      1802628.40     13927523.28
      1802635.62     13927534.55      1802669.59     13927572.80
      1802674.21     13927585.68      1802675.39     13927600.00
      1802674.23     13927614.31      1802669.62     13927627.18
      1802633.19     13927668.92      1802627.29     13927680.93
      1802625.09     13927695.03      1802625.00     13928225.00

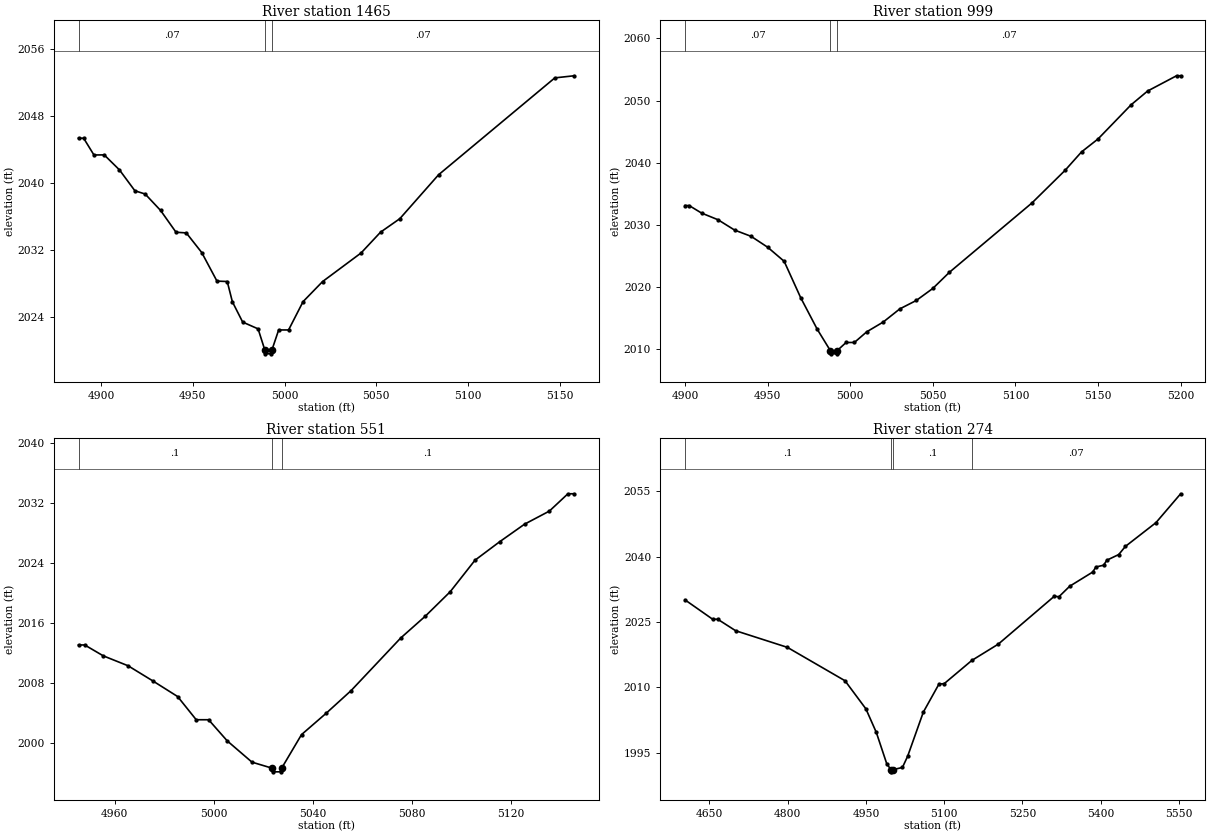
Type RM Length L Ch R = 1,1465,466,466,466
BEGIN DESCRIPTION:
Stream0158 3.0
END DESCRIPTION:
XS GIS Cut Line= 3
      1802625.02     13926775.01      1802725.00     13926825.00
      1802875.00     13926775.00
#Sta/Elev= 30
  4887.8 2045.37  4890.6 2045.37  4896.2 2043.37  4901.8 2043.38  4910.1 2041.59
  4918.5 2039.10  4924.1 2038.71  4932.5 2036.75  4940.9 2034.15  4946.5 2034.07
  4954.9 2031.73  4963.2 2028.32  4968.8 2028.27  4971.6 2025.85  4977.2 2023.43
  4985.6 2022.62  4989.2 2020.14  4989.4 2019.64  4992.9 2019.64  4993.2 2020.14
  4996.8 2022.49  5002.2 2022.49  5010.1 2025.87  5020.7 2028.26  5041.7 2031.68
  5052.3 2034.16  5062.8 2035.77  5083.9 2041.01  5147.2 2052.57  5157.7 2052.82
#Mann=3,-1,0
  4887.8    0.07       0  4989.2    0.05       0  4993.2    0.07       0
Bank Sta=4989.2,4993.2
Exp/Cntr=0.3,0.1

Type RM Length L Ch R = 1,999,448,448,448
BEGIN DESCRIPTION:
Stream0158 2.0
END DESCRIPTION:
XS GIS Cut Line= 3
      1802575.03     13927275.00      1802675.00     13927275.00
      1802875.03     13927275.00
#Sta/Elev= 30
  4900.0 2033.08  4902.5 2033.08  4910.0 2031.87  4920.0 2030.79  4930.0 2029.13
  4940.0 2028.12  4950.0 2026.37  4960.0 2024.10  4970.0 2018.24  4980.0 2013.16
  4988.0 2009.69  4988.2 2009.19  4991.7 2009.19  4992.0 2009.69  4997.5 2011.02
  5002.5 2011.02  5010.0 2012.74  5020.0 2014.32  5030.0 2016.43  5040.0 2017.79
  5050.0 2019.73  5060.0 2022.32  5110.0 2033.50  5130.0 2038.74  5140.0 2041.72
  5150.0 2043.81  5170.0 2049.31  5180.0 2051.53  5197.5 2053.99  5200.0 2053.99
#Mann=3,-1,0
  4900.0    0.07       0  4988.0    0.05       0  4992.0    0.07       0
Bank Sta=4988,4992
Exp/Cntr=0.3,0.1

Type RM Length L Ch R = 1,551,277,277,277
BEGIN DESCRIPTION:
Stream0158 1.0
END DESCRIPTION:
XS GIS Cut Line= 3
      1802575.00     13927675.00      1802625.00     13927675.00
      1802775.00     13927675.00
#Sta/Elev= 26
  4945.4 2013.10  4947.9 2013.10  4955.4 2011.65  4965.4 2010.33  4975.4 2008.31
  4985.4 2006.23  4992.9 2003.14  4997.9 2003.14  5005.4 2000.33  5015.4 1997.49
  5023.4 1996.70  5023.7 1996.20  5027.2 1996.20  5027.4 1996.70  5035.4 2001.16
  5045.4 2004.02  5055.4 2007.02  5075.4 2014.02  5085.4 2016.95  5095.4 2020.19
  5105.4 2024.39  5115.4 2026.86  5125.4 2029.19  5135.4 2030.93  5142.9 2033.24
  5145.4 2033.24
#Mann=3,-1,0
  4945.4     0.1       0  5023.4    0.05       0  5027.4     0.1       0
Bank Sta=5023.4,5027.4
Exp/Cntr=0.3,0.1

Type RM Length L Ch R = 1,274,0,0,0
BEGIN DESCRIPTION:
Stream0158 0.0
END DESCRIPTION:
XS GIS Cut Line= 4
      1802357.35     13927739.55      1802468.93     13927952.53
      1802828.73     13927950.09      1803110.77     13927744.10
#Sta/Elev= 30
  4603.5 2030.05  4656.4 2025.61  4666.1 2025.61  4700.5 2022.97  4799.5 2019.16
  4910.0 2011.49  4950.0 2005.04  4970.0 1999.62  4990.0 1992.42  4998.0 1991.08
  4998.3 1990.58  5002.0 1991.08  5020.0 1991.59  5030.0 1994.16  5060.0 2004.28
  5090.0 2010.73  5100.0 2010.82  5152.9 2016.15  5203.7 2019.90  5311.2 2030.91
  5319.7 2030.76  5340.5 2033.19  5384.5 2036.44  5390.7 2037.61  5405.4 2038.01
  5411.6 2039.16  5434.4 2040.46  5447.1 2042.32  5505.8 2047.79  5553.0 2054.41
#Mann=4,-1,0
  4603.5     0.1       0  4998.0    0.05       0  5002.0     0.1       0
  5152.9    0.07       0
Bank Sta=4998,5002
Exp/Cntr=0.3,0.1

Chan Stop Cuts=-1