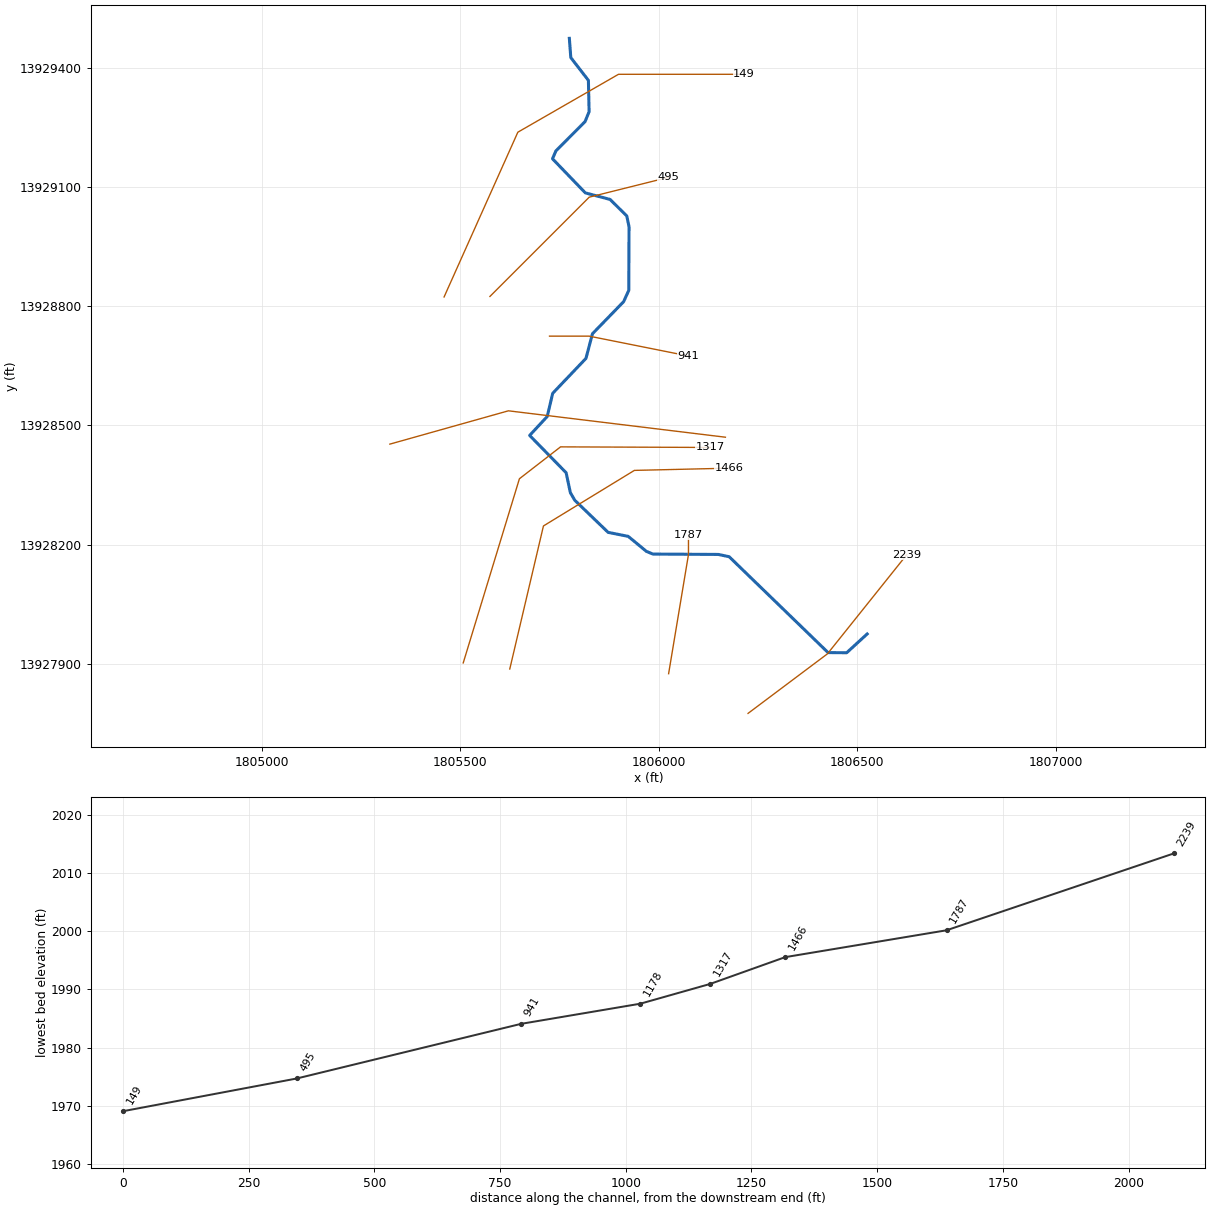
--- Stream0159.prj (project) ---

Proj Title=Stream0159 Base Level Engineering
Current Plan=p01
Default Exp/Contr=0.3,0.1
English Units
Geom File=g01
Flow File=f01
Plan File=p01
BEGIN DESCRIPTION:
Stream0159
END DESCRIPTION:

--- Stream0159.p01 (plan) ---

Plan Title=Multiple Run
Short Identifier=Multiple
Geom File=g01
Flow File=f01
Subcritical Flow
K Sum by GR= 0
Std Step Tol= 0.01
Critical Tol= 0.01
Num of Std Step Trials= 20
Max Error Tol= 0.3
Flow Tol Ratio= 0.001
Split Flow NTrial= 30
Split Flow Tol= 0.02
Split Flow Ratio= 0.02
Log Output Level= 0
Friction Slope Method= 1
Unsteady Friction Slope Method= 2
Unsteady Bridges Friction Slope Method= 1
Parabolic Critical Depth
Global Vel Dist=  1 , 1 , 1
Global Log Level= 0
CheckData=True
Encroach Param= -1, 0, 0, 0
BEGIN DESCRIPTION:
Multiple Run
END DESCRIPTION:

--- Stream0159.f01 (steady flow) ---

Flow Title=Multiple
Number of Profiles=7
Profile Names=10-year,25-year,50-year,1pct_min,100-year,1pct_plu,500-year
River Rch & RM= Stream0159,Reach-1,2239
    1007    1736    2437    1655    3302    6588    5991
Boundary for River Rch & Prof#=Stream0159,Reach-1,1
Up Type=0
Dn Type=3
Dn Slope=0.005
Boundary for River Rch & Prof#=Stream0159,Reach-1,2
Up Type=0
Dn Type=3
Dn Slope=0.005
Boundary for River Rch & Prof#=Stream0159,Reach-1,3
Up Type=0
Dn Type=3
Dn Slope=0.005
Boundary for River Rch & Prof#=Stream0159,Reach-1,4
Up Type=0
Dn Type=3
Dn Slope=0.005
Boundary for River Rch & Prof#=Stream0159,Reach-1,5
Up Type=0
Dn Type=3
Dn Slope=0.005
Boundary for River Rch & Prof#=Stream0159,Reach-1,6
Up Type=0
Dn Type=3
Dn Slope=0.005
Boundary for River Rch & Prof#=Stream0159,Reach-1,7
Up Type=0
Dn Type=3
Dn Slope=0.005

--- Stream0159.g01 (geometry) ---

Geom Title=Existing Conditions

River Reach=Stream0159,Reach-1
Reach XY= 30
      1806525.00     13927975.00      1806473.38     13927927.67
      1806426.58     13927928.07      1806177.45     13928169.54
      1806150.12     13928175.29      1805985.50     13928176.20
      1805968.92     13928183.09      1805923.25     13928220.78
      1805872.69     13928230.82      1805788.62     13928311.76
      1805777.52     13928331.03      1805766.89     13928381.07
      1805675.00     13928475.00      1805719.30     13928522.65
      1805733.07     13928581.08      1805816.82     13928668.96
      1805833.18     13928731.04      1805911.60     13928811.69
      1805924.62     13928840.16      1805925.33     13929000.21
      1805919.64     13929027.70      1805877.57     13929069.26
      1805815.29     13929085.79      1805732.59     13929171.65
      1805741.23     13929191.65      1805814.52     13929265.21
      1805824.75     13929290.21      1805822.98     13929369.08
      1805778.65     13929426.51      1805775.00     13929475.00

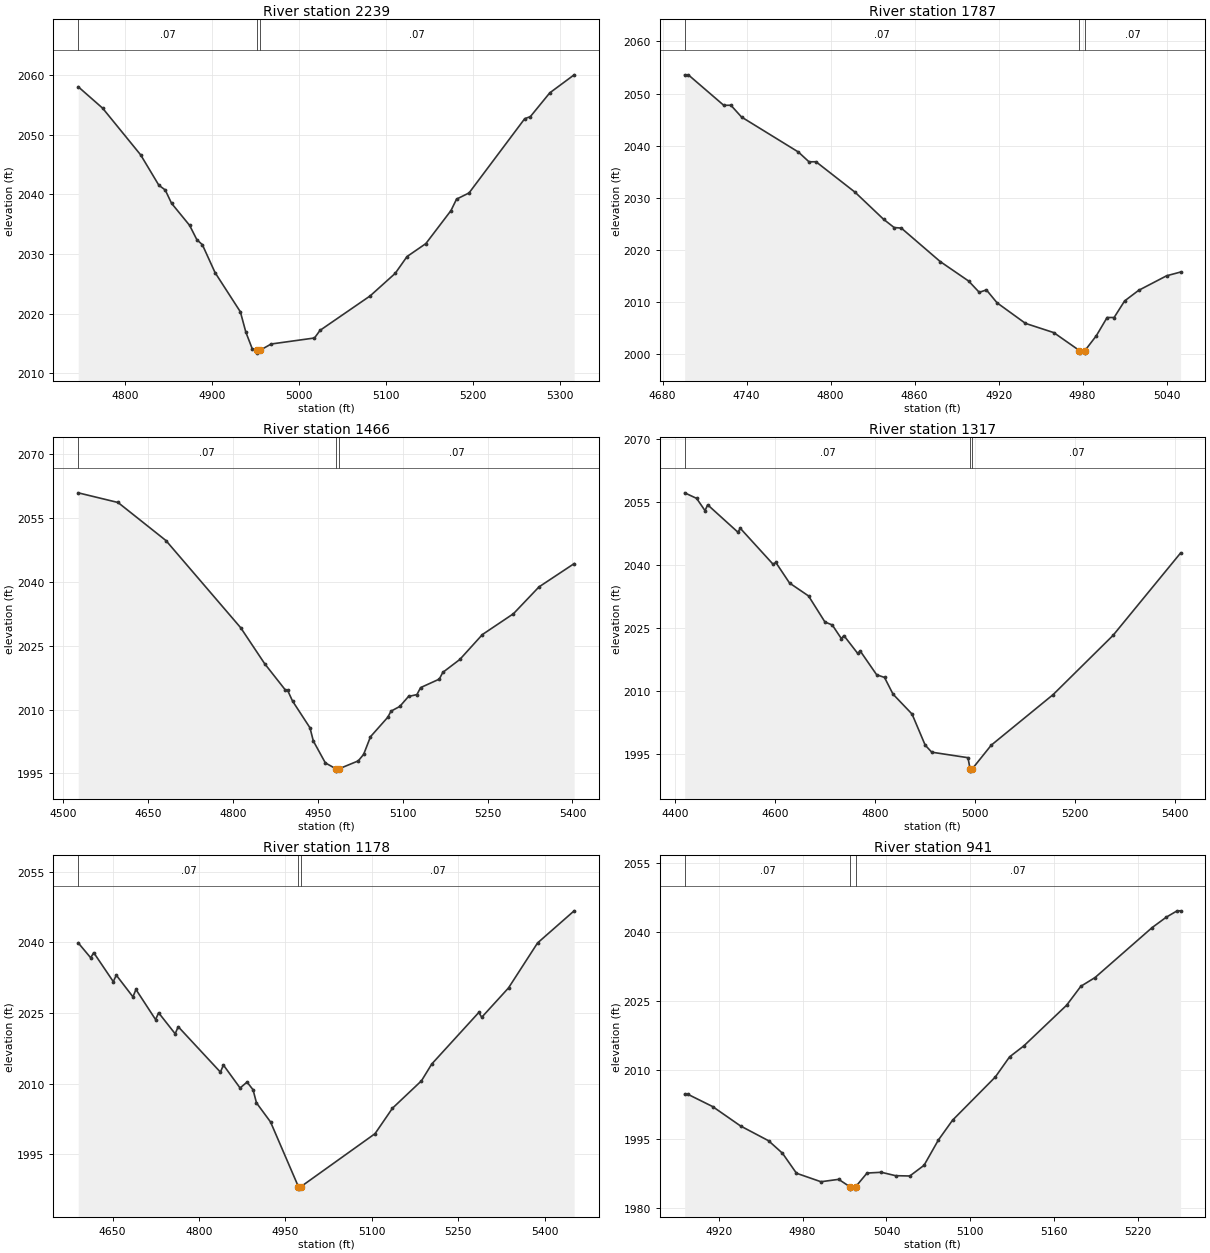
Type RM Length L Ch R = 1,2239,452,452,452
BEGIN DESCRIPTION:
Stream0160 2.0
END DESCRIPTION:
XS GIS Cut Line= 3
      1806225.02     13927775.02      1806425.00     13927925.00
      1806624.98     13928174.98
#Sta/Elev= 30
  4746.4 2058.06  4774.5 2054.46  4818.2 2046.63  4839.1 2041.54  4846.4 2040.75
  4853.7 2038.51  4874.5 2034.80  4882.8 2032.40  4889.1 2031.57  4903.7 2026.89
  4932.8 2020.31  4939.1 2016.90  4946.4 2014.13  4951.7 2013.88  4951.9 2013.38
  4955.7 2013.88  4968.2 2014.91  5018.0 2015.92  5024.4 2017.20  5082.0 2022.98
  5110.8 2026.76  5124.4 2029.58  5146.0 2031.75  5174.9 2037.29  5181.3 2039.21
  5195.7 2040.25  5259.7 2052.71  5266.1 2053.04  5288.5 2057.04  5316.5 2060.06
#Mann=3,-1,0
  4746.4    0.07       0  4951.7    0.05       0  4955.7    0.07       0
Bank Sta=4951.7,4955.7
Exp/Cntr=0.3,0.1

Type RM Length L Ch R = 1,1787,321,321,321
BEGIN DESCRIPTION:
Stream0160 1.0
END DESCRIPTION:
XS GIS Cut Line= 3
      1806024.99     13927874.95      1806075.00     13928175.00
      1806075.00     13928225.01
#Sta/Elev= 30
  4695.8 2053.60  4698.4 2053.60  4723.7 2047.75  4728.8 2047.76  4736.4 2045.50
  4777.0 2038.78  4784.6 2036.90  4789.6 2036.91  4817.5 2031.06  4837.8 2025.88
  4845.4 2024.28  4850.5 2024.18  4878.3 2017.75  4898.6 2014.01  4906.2 2011.84
  4911.3 2012.31  4918.9 2009.83  4939.2 2005.88  4959.4 2004.11  4977.7 2000.67
  4978.0 2000.17  4981.5 2000.17  4981.7 2000.67  4989.8 2003.51  4997.5 2007.01
  5002.5 2007.01  5010.0 2010.19  5020.0 2012.22  5040.0 2015.02  5050.0 2015.74
#Mann=3,-1,0
  4695.8    0.07       0  4977.7    0.05       0  4981.7    0.07       0
Bank Sta=4977.7,4981.7
Exp/Cntr=0.3,0.1

Type RM Length L Ch R = 1,1466,149,149,149
BEGIN DESCRIPTION:
Stream0160 0.0
END DESCRIPTION:
XS GIS Cut Line= 4
      1805624.97     13927886.78      1805709.77     13928247.01
      1805938.78     13928386.93      1806177.17     13928392.52
#Sta/Elev= 30
  4526.1 2060.89  4596.5 2058.62  4681.2 2049.69  4813.5 2029.20  4855.8 2020.77
  4892.6 2014.56  4896.2 2014.56  4905.0 2012.02  4935.9 2005.72  4941.8 2002.63
  4963.1 1997.48  4982.4 1996.05  4982.7 1995.55  4986.4 1996.05  5021.2 1997.95
  5030.8 1999.49  5042.9 2003.63  5073.4 2008.19  5079.2 2009.63  5094.7 2010.74
  5110.1 2013.08  5125.0 2013.52  5131.5 2015.16  5164.5 2017.15  5170.8 2018.74
  5200.8 2021.76  5240.8 2027.62  5295.7 2032.51  5340.8 2038.80  5403.0 2044.27
#Mann=3,-1,0
  4526.1    0.07       0  4982.4    0.05       0  4986.4    0.07       0
Bank Sta=4982.4,4986.4
Exp/Cntr=0.3,0.1

Type RM Length L Ch R = 1,1317,139,139,139
BEGIN DESCRIPTION:
Stream0160 0.1
END DESCRIPTION:
XS GIS Cut Line= 4
      1805507.75     13927902.14      1805649.24     13928365.88
      1805752.85     13928446.18      1806130.42     13928444.70
#Sta/Elev= 30
  4418.7 2057.24  4442.6 2055.92  4459.5 2052.99  4464.7 2054.39  4525.1 2047.89
  4530.3 2048.77  4596.0 2040.20  4601.2 2040.67  4628.8 2035.75  4666.8 2032.68
  4699.7 2026.47  4714.4 2025.76  4732.5 2022.53  4737.7 2023.23  4765.3 2018.99
  4770.5 2019.54  4803.3 2013.90  4819.0 2013.27  4836.1 2009.28  4874.2 2004.54
  4900.5 1997.14  4913.7 1995.46  4986.2 1994.15  4990.5 1991.45  4990.7 1990.95
  4994.5 1991.45  5032.8 1997.13  5156.8 2009.18  5276.8 2023.28  5412.2 2042.92
#Mann=3,-1,0
  4418.7    0.07       0  4990.5    0.05       0  4994.5    0.07       0
Bank Sta=4990.5,4994.5
Exp/Cntr=0.3,0.1

Type RM Length L Ch R = 1,1178,237,237,237
BEGIN DESCRIPTION:
Stream0159 3.0
END DESCRIPTION:
XS GIS Cut Line= 3
      1805322.94     13928453.06      1805621.55     13928536.98
      1806168.04     13928470.50
#Sta/Elev= 30
  4590.3 2039.92  4612.0 2036.74  4617.2 2037.84  4651.2 2031.67  4656.4 2033.05
  4685.3 2028.44  4690.5 2030.01  4724.6 2023.60  4729.8 2025.06  4758.6 2020.58
  4763.8 2022.10  4837.1 2012.43  4842.3 2013.94  4871.2 2009.06  4883.3 2010.31
  4893.7 2008.69  4899.7 2005.89  4924.1 2001.83  4972.5 1988.05  4972.7 1987.55
  4976.5 1988.05  5105.4 1999.34  5135.7 2004.76  5186.0 2010.58  5203.9 2014.16
  5285.6 2025.13  5290.6 2024.09  5337.1 2030.34  5387.5 2039.90  5451.0 2046.73
#Mann=3,-1,0
  4590.3    0.07       0  4972.5    0.05       0  4976.5    0.07       0
Bank Sta=4972.5,4976.5
Exp/Cntr=0.3,0.1

Type RM Length L Ch R = 1,941,446,446,446
BEGIN DESCRIPTION:
Stream0159 2.0
END DESCRIPTION:
XS GIS Cut Line= 3
      1805725.05     13928725.00      1805825.00     13928725.00
      1806075.00     13928675.00
#Sta/Elev= 30
  4895.6 2004.71  4898.1 2004.71  4915.6 2002.07  4935.6 1997.84  4955.6 1994.63
  4965.6 1991.90  4975.6 1987.55  4993.1 1985.70  5005.8 1986.22  5013.9 1984.59
  5014.2 1984.09  5017.7 1984.09  5017.9 1984.59  5026.1 1987.59  5036.3 1987.76
  5046.5 1987.02  5056.7 1986.95  5066.9 1989.28  5077.1 1994.76  5087.3 1999.10
  5117.9 2008.51  5128.1 2012.89  5138.3 2015.28  5168.9 2024.13  5179.1 2028.26
  5189.3 2030.17  5230.1 2041.04  5240.3 2043.32  5248.0 2044.69  5250.5 2044.69
#Mann=3,-1,0
  4895.6    0.07       0  5013.9    0.05       0  5017.9    0.07       0
Bank Sta=5013.9,5017.9
Exp/Cntr=0.3,0.1

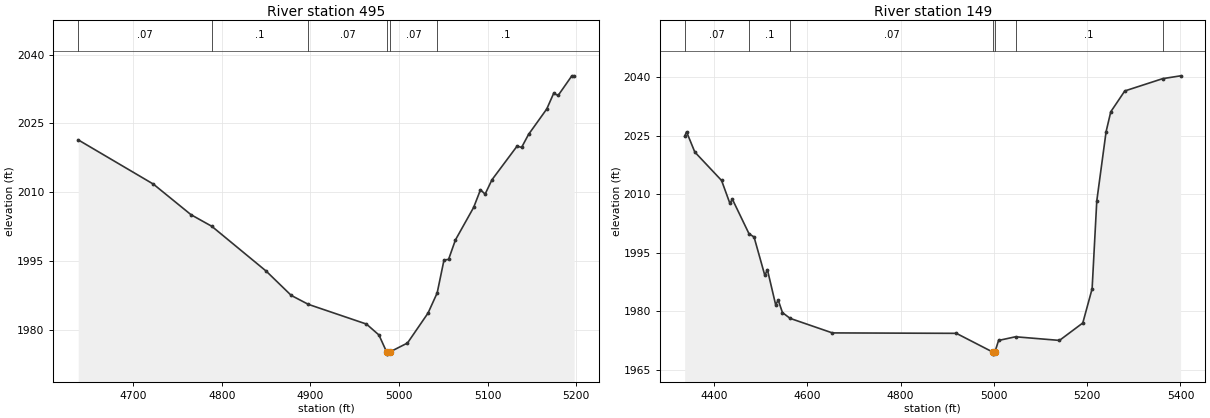
Type RM Length L Ch R = 1,495,346,346,346
BEGIN DESCRIPTION:
Stream0159 1.0
END DESCRIPTION:
XS GIS Cut Line= 3
      1805575.01     13928825.01      1805825.00     13929075.00
      1806025.00     13929125.00
#Sta/Elev= 30
  4637.9 2021.40  4722.7 2011.76  4765.2 2005.09  4788.6 2002.57  4850.0 1992.80
  4878.3 1987.50  4897.6 1985.55  4963.2 1981.25  4977.3 1978.87  4985.9 1975.20
  4986.2 1974.70  4989.9 1975.20  5009.5 1977.12  5032.7 1983.65  5043.0 1988.03
  5050.7 1995.20  5055.9 1995.36  5063.6 1999.58  5084.2 2006.69  5091.9 2010.53
  5097.1 2009.57  5104.8 2012.69  5133.2 2020.04  5138.3 2019.76  5146.1 2022.58
  5166.7 2028.14  5174.4 2031.51  5179.6 2031.10  5195.0 2035.36  5197.6 2035.36
#Mann=6,-1,0
  4637.9    0.07       0  4788.6     0.1       0  4897.6    0.07       0
  4985.9    0.05       0  4989.9    0.07       0  5043.0     0.1       0
Bank Sta=4985.9,4989.9
Exp/Cntr=0.3,0.1

Type RM Length L Ch R = 1,149,0,0,0
BEGIN DESCRIPTION:
Stream0159 0.0
END DESCRIPTION:
XS GIS Cut Line= 4
      1805459.54     13928823.69      1805645.30     13929238.60
      1805898.77     13929384.44      1806214.74     13929384.44
#Sta/Elev= 30
  4337.3 2024.82  4341.3 2025.95  4359.0 2020.78  4416.4 2013.50  4434.1 2007.68
  4439.6 2008.69  4475.2 1999.87  4486.0 1999.04  4509.1 1989.21  4514.6 1990.69
  4532.3 1981.70  4537.8 1982.88  4546.9 1979.69  4563.3 1978.22  4653.8 1974.50
  4919.6 1974.39  4998.1 1969.57  4998.4 1969.07  5002.1 1969.57  5010.1 1972.57
  5046.4 1973.51  5140.6 1972.58  5190.6 1977.04  5210.6 1985.79  5220.6 2008.27
  5240.6 2026.01  5250.6 2031.08  5280.6 2036.41  5361.9 2039.56  5400.3 2040.28
#Mann=7,-1,0
  4337.3    0.07       0  4475.2     0.1       0  4563.3    0.07       0
  4998.1    0.05       0  5002.1    0.07       0  5046.4     0.1       0
  5361.9    0.07       0
Bank Sta=4998.1,5002.1
Exp/Cntr=0.3,0.1

Chan Stop Cuts=-1