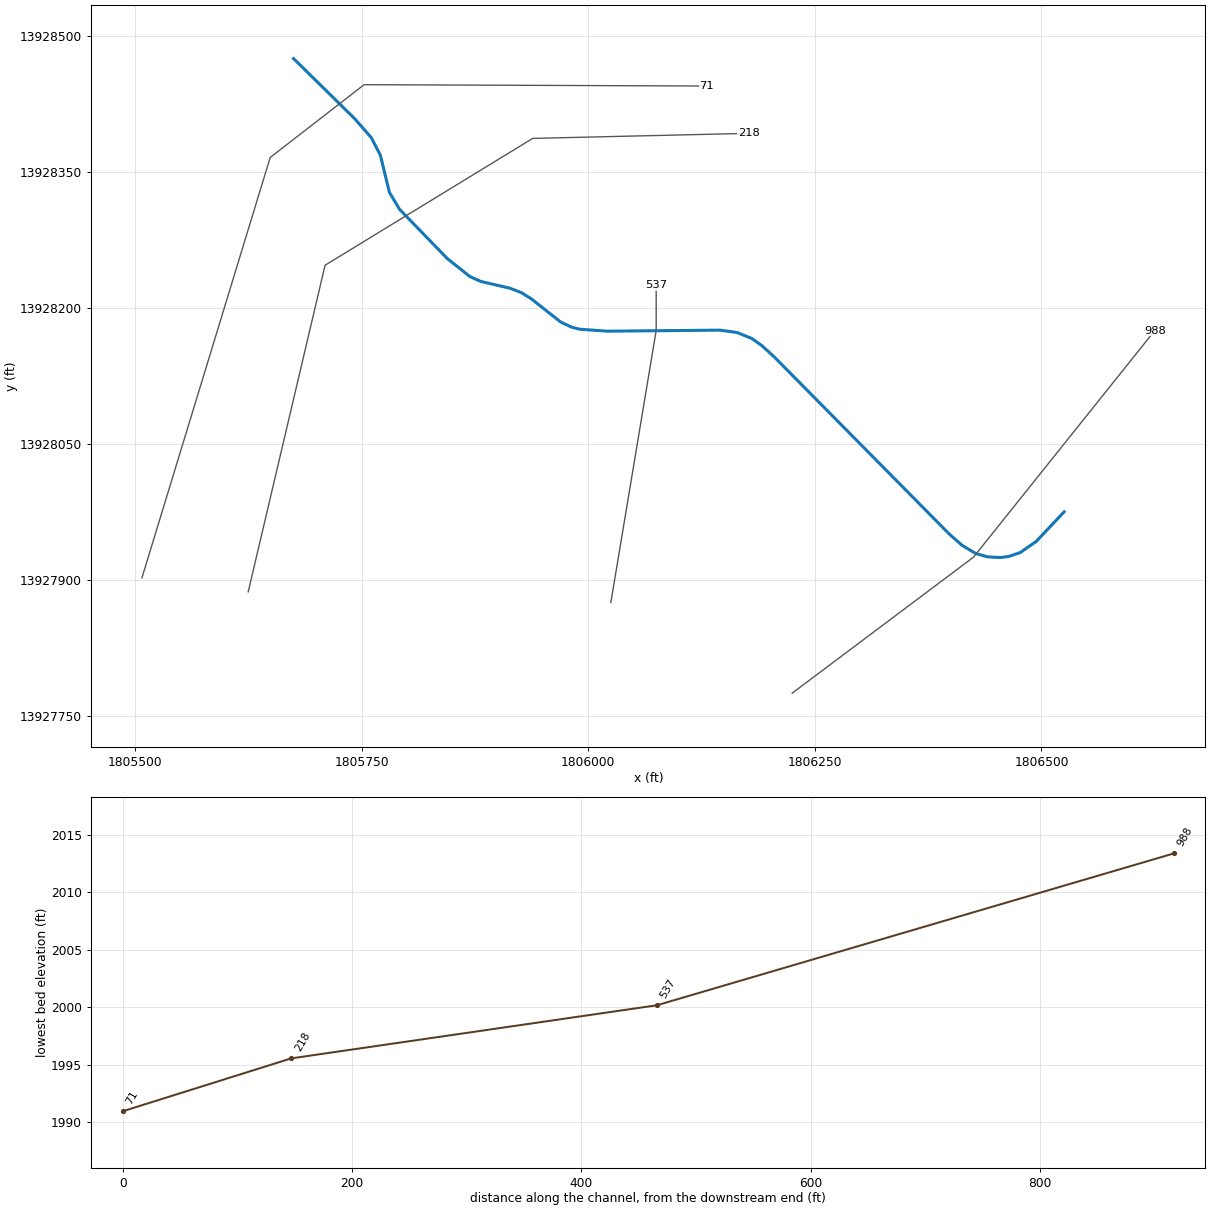
--- Stream0160.prj (project) ---

Proj Title=Stream0160 Base Level Engineering
Current Plan=p01
Default Exp/Contr=0.3,0.1
English Units
Geom File=g01
Flow File=f01
Plan File=p01
BEGIN DESCRIPTION:
Stream0160
END DESCRIPTION:

--- Stream0160.p01 (plan) ---

Plan Title=Multiple Run
Short Identifier=Multiple
Geom File=g01
Flow File=f01
Subcritical Flow
K Sum by GR= 0
Std Step Tol= 0.01
Critical Tol= 0.01
Num of Std Step Trials= 20
Max Error Tol= 0.3
Flow Tol Ratio= 0.001
Split Flow NTrial= 30
Split Flow Tol= 0.02
Split Flow Ratio= 0.02
Log Output Level= 0
Friction Slope Method= 1
Unsteady Friction Slope Method= 2
Unsteady Bridges Friction Slope Method= 1
Parabolic Critical Depth
Global Vel Dist=  1 , 1 , 1
Global Log Level= 0
CheckData=True
Encroach Param= -1, 0, 0, 0
BEGIN DESCRIPTION:
Multiple Run
END DESCRIPTION:

--- Stream0160.f01 (steady flow) ---

Flow Title=Multiple
Number of Profiles=7
Profile Names=10-year,25-year,50-year,1pct_min,100-year,1pct_plu,500-year
River Rch & RM= Stream0160,Reach-1,988
    1007    1736    2437    1655    3302    6588    5991
Boundary for River Rch & Prof#=Stream0160,Reach-1,1
Up Type=0
Dn Type=3
Dn Slope=0.005
Boundary for River Rch & Prof#=Stream0160,Reach-1,2
Up Type=0
Dn Type=3
Dn Slope=0.005
Boundary for River Rch & Prof#=Stream0160,Reach-1,3
Up Type=0
Dn Type=3
Dn Slope=0.005
Boundary for River Rch & Prof#=Stream0160,Reach-1,4
Up Type=0
Dn Type=3
Dn Slope=0.005
Boundary for River Rch & Prof#=Stream0160,Reach-1,5
Up Type=0
Dn Type=3
Dn Slope=0.005
Boundary for River Rch & Prof#=Stream0160,Reach-1,6
Up Type=0
Dn Type=3
Dn Slope=0.005
Boundary for River Rch & Prof#=Stream0160,Reach-1,7
Up Type=0
Dn Type=3
Dn Slope=0.005

--- Stream0160.g01 (geometry) ---

Geom Title=Existing Conditions

River Reach=Stream0160,Reach-1
Reach XY= 30
      1806525.00     13927975.00      1806494.09     13927942.25
      1806476.53     13927930.07      1806463.82     13927925.79
      1806454.54     13927924.60      1806440.44     13927925.35
      1806427.29     13927929.14      1806412.22     13927938.22
      1806398.16     13927950.64      1806205.30     13928145.82
      1806191.50     13928158.43      1806180.56     13928166.17
      1806164.31     13928172.82      1806145.32     13928175.43
      1806020.94     13928174.29      1805990.40     13928176.48
      1805981.50     13928178.83      1805969.70     13928184.36
      1805937.38     13928209.88      1805926.21     13928216.87
      1805913.76     13928221.67      1805881.57     13928229.14
      1805869.63     13928234.47      1805844.62     13928254.35
      1805792.03     13928308.61      1805780.77     13928327.35
      1805770.78     13928368.38      1805760.77     13928387.76
      1805742.45     13928408.67      1805675.00     13928475.00

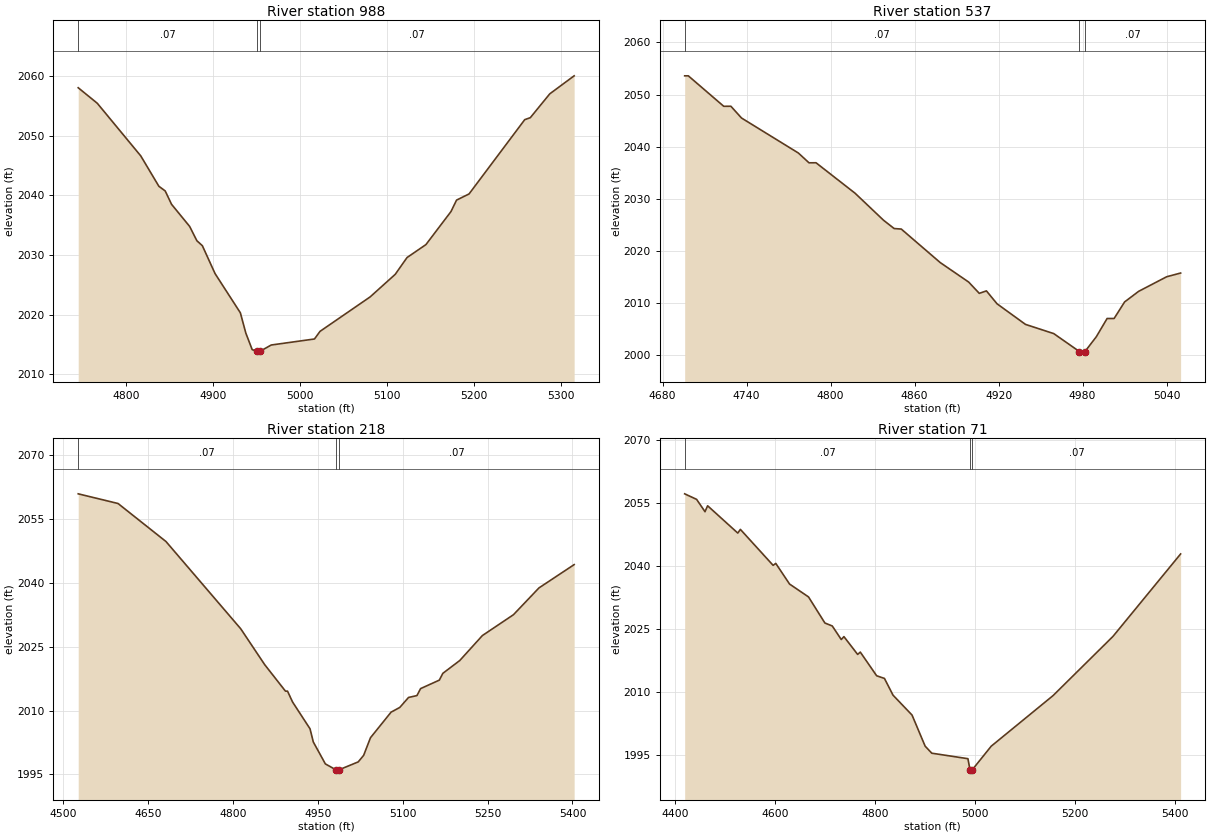
Type RM Length L Ch R = 1,988,451,451,451
BEGIN DESCRIPTION:
Stream0160 2.0
END DESCRIPTION:
XS GIS Cut Line= 3
      1806225.01     13927775.01      1806425.00     13927925.00
      1806624.98     13928174.97
#Sta/Elev= 30
  4745.1 2058.06  4767.0 2055.46  4817.0 2046.63  4837.8 2041.54  4845.1 2040.75
  4852.4 2038.51  4873.2 2034.80  4881.5 2032.40  4887.8 2031.57  4902.4 2026.89
  4931.5 2020.31  4937.8 2016.90  4945.1 2014.13  4950.4 2013.88  4950.6 2013.38
  4954.4 2013.88  4967.0 2014.91  5016.7 2015.92  5023.1 2017.20  5080.7 2022.98
  5109.5 2026.76  5123.1 2029.58  5144.8 2031.75  5173.6 2037.29  5180.0 2039.21
  5194.4 2040.25  5258.4 2052.71  5264.8 2053.04  5287.2 2057.04  5315.2 2060.06
#Mann=3,-1,0
  4745.1    0.07       0  4950.4    0.05       0  4954.4    0.07       0
Bank Sta=4950.4,4954.4
Exp/Cntr=0.3,0.1

Type RM Length L Ch R = 1,537,319,319,319
BEGIN DESCRIPTION:
Stream0160 1.0
END DESCRIPTION:
XS GIS Cut Line= 3
      1806024.99     13927874.95      1806075.00     13928175.00
      1806075.00     13928225.01
#Sta/Elev= 30
  4695.8 2053.60  4698.4 2053.60  4723.7 2047.75  4728.8 2047.76  4736.4 2045.50
  4777.0 2038.78  4784.6 2036.90  4789.6 2036.91  4817.5 2031.06  4837.8 2025.88
  4845.4 2024.28  4850.5 2024.18  4878.3 2017.75  4898.6 2014.01  4906.2 2011.84
  4911.3 2012.31  4918.9 2009.83  4939.2 2005.88  4959.4 2004.11  4977.7 2000.67
  4978.0 2000.17  4981.5 2000.17  4981.7 2000.67  4989.8 2003.51  4997.5 2007.01
  5002.5 2007.01  5010.0 2010.19  5020.0 2012.22  5040.0 2015.02  5050.0 2015.74
#Mann=3,-1,0
  4695.8    0.07       0  4977.7    0.05       0  4981.7    0.07       0
Bank Sta=4977.7,4981.7
Exp/Cntr=0.3,0.1

Type RM Length L Ch R = 1,218,147,147,147
BEGIN DESCRIPTION:
Stream0160 0.0
END DESCRIPTION:
XS GIS Cut Line= 4
      1805624.97     13927886.76      1805709.77     13928247.01
      1805938.78     13928386.93      1806177.15     13928392.52
#Sta/Elev= 30
  4526.1 2060.89  4596.5 2058.62  4681.3 2049.69  4813.5 2029.20  4855.9 2020.77
  4892.6 2014.56  4896.2 2014.56  4905.1 2012.02  4936.0 2005.72  4941.8 2002.63
  4963.1 1997.48  4982.4 1996.05  4982.7 1995.55  4986.2 1995.55  4986.4 1996.05
  5021.2 1997.95  5030.8 1999.49  5042.9 2003.63  5079.3 2009.63  5094.7 2010.74
  5110.2 2013.08  5125.0 2013.52  5131.5 2015.16  5164.6 2017.15  5170.8 2018.74
  5200.8 2021.76  5240.8 2027.62  5295.7 2032.51  5340.8 2038.80  5403.0 2044.27
#Mann=3,-1,0
  4526.1    0.07       0  4982.4    0.05       0  4986.4    0.07       0
Bank Sta=4982.4,4986.4
Exp/Cntr=0.3,0.1

Type RM Length L Ch R = 1,71,0,0,0
BEGIN DESCRIPTION:
Stream0160 0.1
END DESCRIPTION:
XS GIS Cut Line= 4
      1805507.76     13927902.17      1805649.24     13928365.88
      1805752.85     13928446.18      1806130.45     13928444.70
#Sta/Elev= 30
  4418.4 2057.24  4442.3 2055.92  4459.1 2052.99  4464.4 2054.39  4524.8 2047.89
  4530.0 2048.77  4595.6 2040.20  4600.9 2040.67  4628.5 2035.75  4666.5 2032.68
  4699.3 2026.47  4714.1 2025.76  4732.1 2022.53  4737.4 2023.23  4764.9 2018.99
  4770.2 2019.54  4803.0 2013.90  4818.6 2013.27  4835.8 2009.28  4873.9 2004.54
  4900.1 1997.14  4913.4 1995.46  4985.8 1994.15  4990.1 1991.45  4990.4 1990.95
  4994.1 1991.45  5032.5 1997.13  5156.4 2009.18  5276.4 2023.28  5411.9 2042.92
#Mann=3,-1,0
  4418.4    0.07       0  4990.1    0.05       0  4994.1    0.07       0
Bank Sta=4990.1,4994.1
Exp/Cntr=0.3,0.1

Chan Stop Cuts=-1