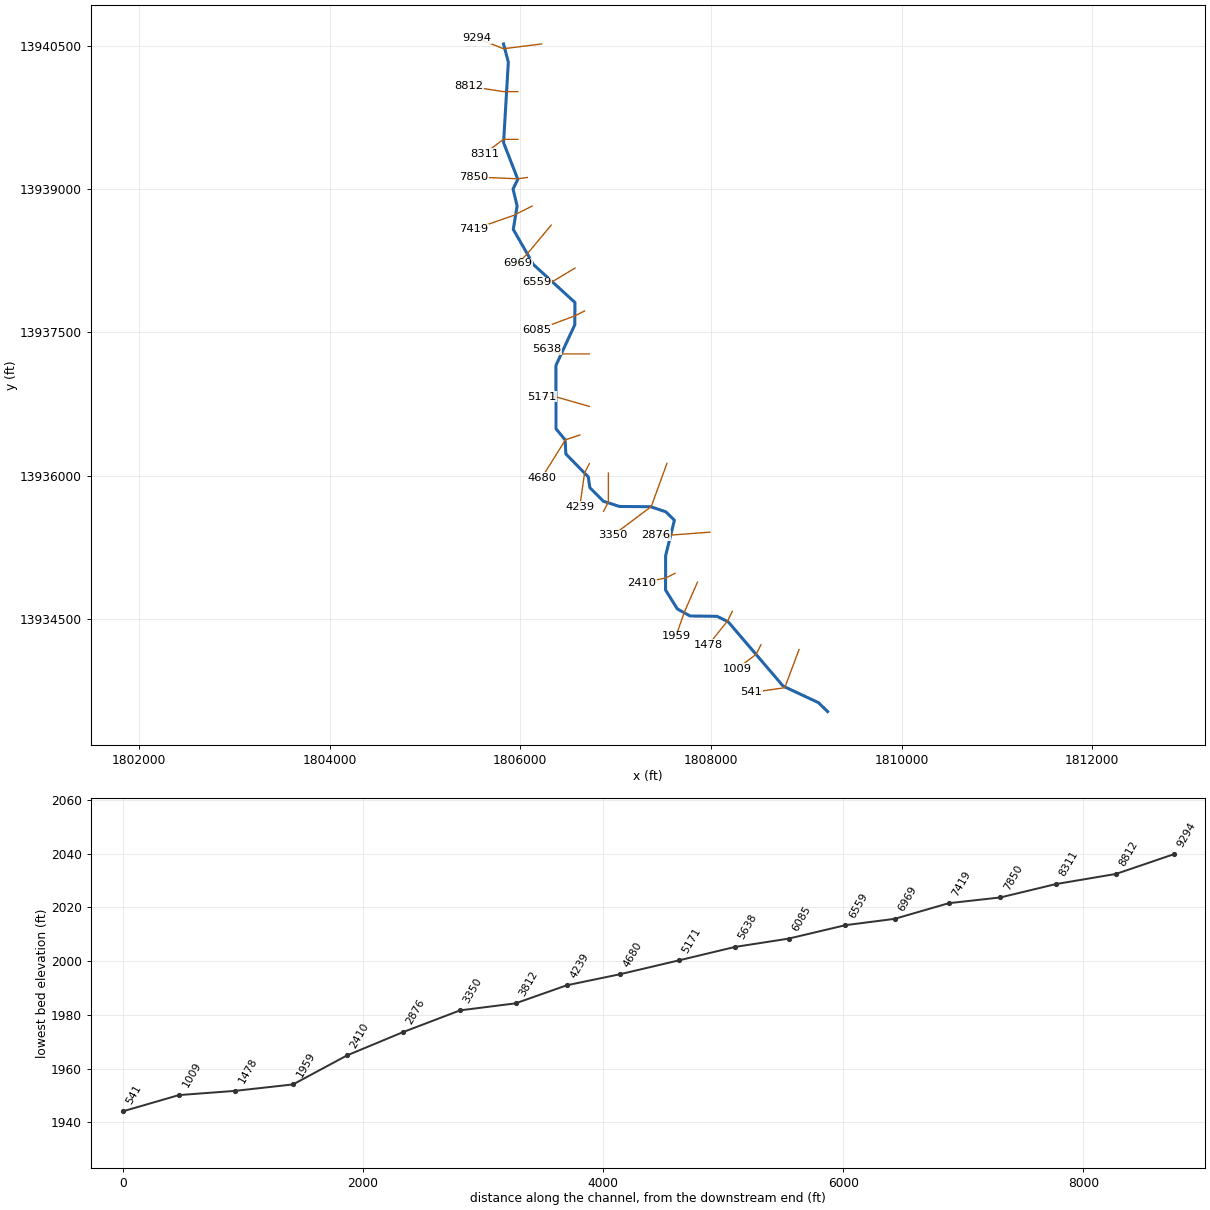
--- Stream0161.prj (project) ---

Proj Title=Stream0161 Base Level Engineering
Current Plan=p01
Default Exp/Contr=0.3,0.1
English Units
Geom File=g01
Flow File=f01
Plan File=p01
BEGIN DESCRIPTION:
Stream0161
END DESCRIPTION:

--- Stream0161.p01 (plan) ---

Plan Title=Multiple Run
Short Identifier=Multiple
Geom File=g01
Flow File=f01
Subcritical Flow
K Sum by GR= 0
Std Step Tol= 0.01
Critical Tol= 0.01
Num of Std Step Trials= 20
Max Error Tol= 0.3
Flow Tol Ratio= 0.001
Split Flow NTrial= 30
Split Flow Tol= 0.02
Split Flow Ratio= 0.02
Log Output Level= 0
Friction Slope Method= 1
Unsteady Friction Slope Method= 2
Unsteady Bridges Friction Slope Method= 1
Parabolic Critical Depth
Global Vel Dist=  1 , 1 , 1
Global Log Level= 0
CheckData=True
Encroach Param= -1, 0, 0, 0
BEGIN DESCRIPTION:
Multiple Run
END DESCRIPTION:

--- Stream0161.f01 (steady flow) ---

Flow Title=Multiple
Number of Profiles=7
Profile Names=10-year,25-year,50-year,1pct_min,100-year,1pct_plu,500-year
River Rch & RM= Stream0161,Reach-1,9294
    1836    3243    4623    3177    6340   12649   11802
River Rch & RM= Stream0161,Reach-1,4239
    2242    4000    5741    3969    7919   15801   14924
Boundary for River Rch & Prof#=Stream0161,Reach-1,1
Up Type=0
Dn Type=3
Dn Slope=0.005
Boundary for River Rch & Prof#=Stream0161,Reach-1,2
Up Type=0
Dn Type=3
Dn Slope=0.005
Boundary for River Rch & Prof#=Stream0161,Reach-1,3
Up Type=0
Dn Type=3
Dn Slope=0.005
Boundary for River Rch & Prof#=Stream0161,Reach-1,4
Up Type=0
Dn Type=3
Dn Slope=0.005
Boundary for River Rch & Prof#=Stream0161,Reach-1,5
Up Type=0
Dn Type=3
Dn Slope=0.005
Boundary for River Rch & Prof#=Stream0161,Reach-1,6
Up Type=0
Dn Type=3
Dn Slope=0.005
Boundary for River Rch & Prof#=Stream0161,Reach-1,7
Up Type=0
Dn Type=3
Dn Slope=0.005

--- Stream0161.g01 (geometry) ---

Geom Title=Existing Conditions

River Reach=Stream0161,Reach-1
Reach XY= 30
      1805825.00     13940525.00      1805875.45     13940335.19
      1805825.52     13939490.22      1805975.29     13939104.83
      1805925.07     13939004.97      1805967.44     13938825.00
      1805927.24     13938580.93      1806138.69     13938212.00
      1806573.95     13937814.57      1806572.74     13937580.94
      1806375.06     13937154.97      1806375.39     13936490.16
      1806471.44     13936373.53      1806478.75     13936226.53
      1806714.48     13935984.79      1806730.52     13935872.57
      1806872.57     13935730.52      1807040.22     13935675.52
      1807369.06     13935672.74      1807527.44     13935619.48
      1807617.53     13935531.08      1807525.52     13935159.78
      1807524.79     13934799.91      1807648.12     13934601.27
      1807780.93     13934527.24      1808064.50     13934523.80
      1808181.06     13934466.86      1808758.33     13933791.65
      1809127.32     13933619.21      1809225.00     13933525.00

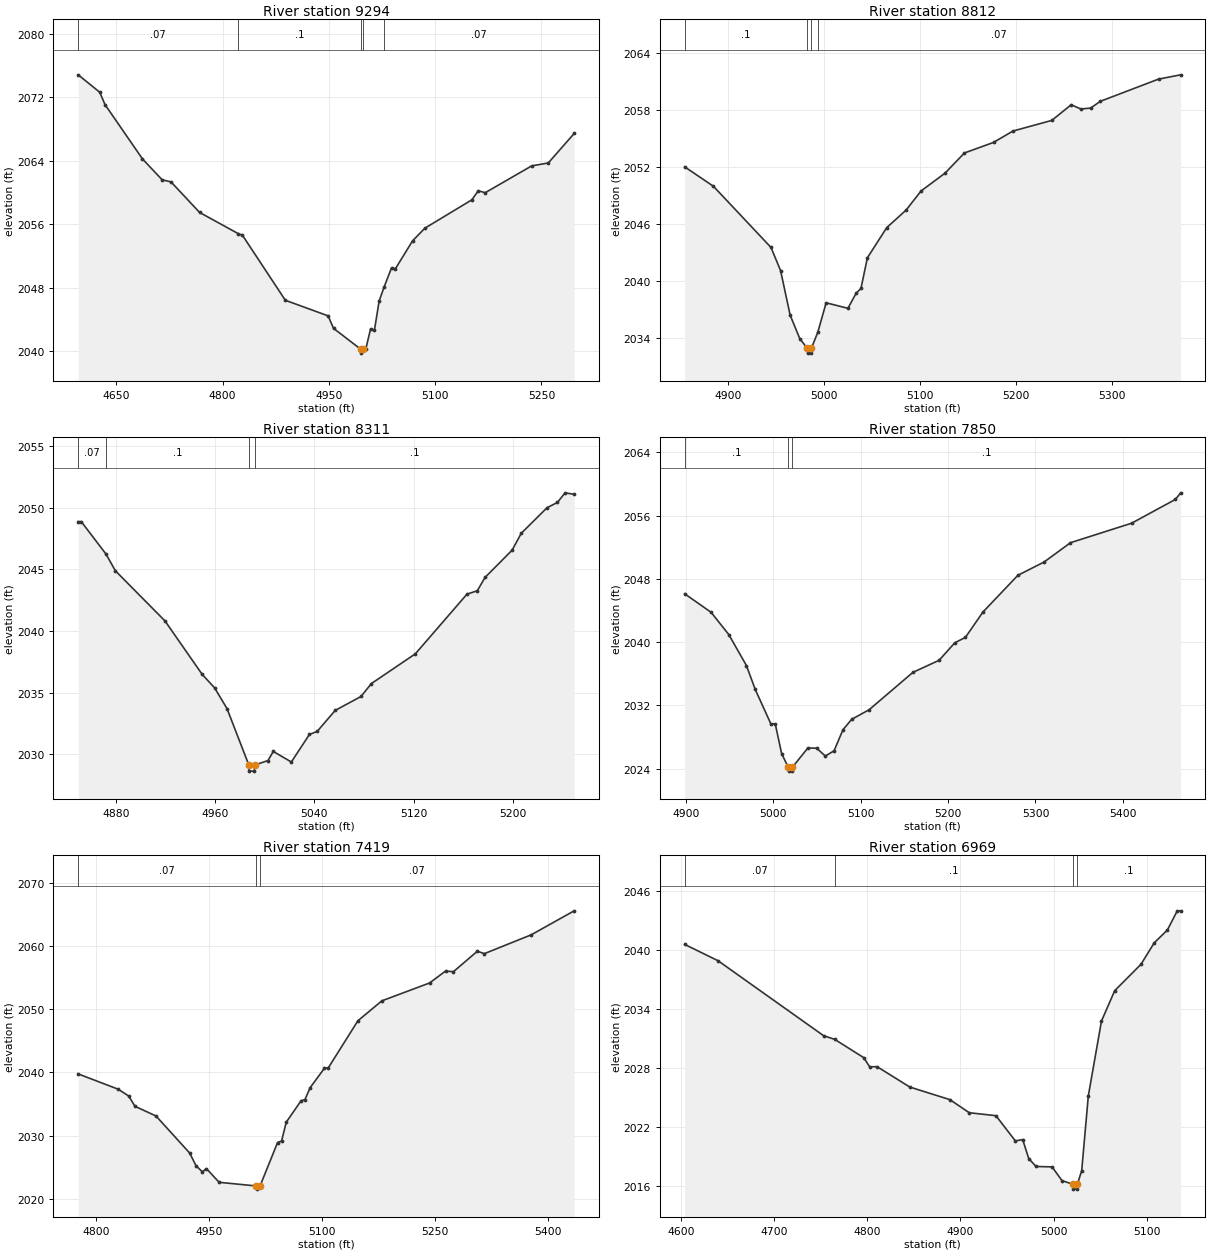
Type RM Length L Ch R = 1,9294,482,482,482
BEGIN DESCRIPTION:
Stream0161 20.0
END DESCRIPTION:
XS GIS Cut Line= 3
      1806225.02     13940525.00      1805825.00     13940475.00
      1805549.28     13940584.78
#Sta/Elev= 30
  4596.2 2074.86  4626.5 2072.67  4634.0 2071.11  4686.9 2064.25  4714.6 2061.62
  4727.2 2061.35  4767.5 2057.50  4821.9 2054.83  4828.0 2054.62  4888.5 2046.42
  4948.9 2044.45  4956.5 2042.88  4994.8 2040.25  4995.1 2039.75  4998.8 2040.25
  5002.0 2040.25  5008.8 2042.80  5014.2 2042.62  5020.9 2046.33  5028.1 2048.14
  5038.4 2050.51  5043.8 2050.39  5068.1 2053.92  5085.4 2055.51  5151.7 2059.09
  5160.8 2060.23  5170.6 2059.99  5236.1 2063.37  5259.6 2063.74  5296.1 2067.46
#Mann=5,-1,0
  4596.2    0.07       0  4821.9     0.1       0  4994.8    0.05       0
  4998.8     0.1       0  5028.1    0.07       0
Bank Sta=4994.8,4998.8
Exp/Cntr=0.3,0.1

Type RM Length L Ch R = 1,8812,501,501,501
BEGIN DESCRIPTION:
Stream0161 19.0
END DESCRIPTION:
XS GIS Cut Line= 3
      1805974.97     13940025.00      1805825.00     13940025.00
      1805462.29     13940081.78
#Sta/Elev= 30
  4854.6 2052.03  4884.6 2049.98  4944.6 2043.54  4954.6 2041.10  4964.6 2036.40
  4974.6 2033.94  4982.5 2032.91  4982.8 2032.41  4986.4 2032.41  4986.7 2032.91
  4993.4 2034.61  5002.1 2037.71  5024.8 2037.13  5033.4 2038.72  5038.4 2039.22
  5045.1 2042.45  5065.3 2045.63  5085.5 2047.48  5101.1 2049.49  5126.0 2051.36
  5146.3 2053.49  5176.6 2054.60  5196.9 2055.80  5237.4 2056.92  5257.6 2058.57
  5267.7 2058.12  5277.9 2058.22  5288.0 2058.93  5348.7 2061.27  5371.7 2061.72
#Mann=4,-1,0
  4854.6     0.1       0  4982.5    0.05       0  4986.7     0.1       0
  4993.4    0.07       0
Bank Sta=4982.5,4986.7
Exp/Cntr=0.3,0.1

Type RM Length L Ch R = 1,8311,461,461,461
BEGIN DESCRIPTION:
Stream0161 18.0
END DESCRIPTION:
XS GIS Cut Line= 3
      1805975.02     13939525.00      1805825.00     13939525.00
      1805625.02     13939375.01
#Sta/Elev= 30
  4849.5 2048.88  4852.0 2048.88  4871.9 2046.25  4879.5 2044.89  4919.5 2040.82
  4949.5 2036.48  4959.5 2035.39  4969.5 2033.71  4987.1 2029.13  4987.4 2028.63
  4991.6 2028.63  4992.0 2029.13  5002.6 2029.49  5006.8 2030.23  5021.4 2029.37
  5036.0 2031.61  5042.2 2031.85  5056.8 2033.56  5077.6 2034.69  5086.0 2035.74
  5121.4 2038.15  5163.1 2043.00  5171.4 2043.27  5177.6 2044.35  5199.5 2046.57
  5206.8 2047.93  5227.6 2050.01  5236.0 2050.44  5242.2 2051.22  5249.5 2051.10
#Mann=4,-1,0
  4849.5    0.07       0  4871.9     0.1       0  4987.1    0.05       0
  4992.0     0.1       0
Bank Sta=4987.1,4992
Exp/Cntr=0.3,0.1

Type RM Length L Ch R = 1,7850,431,431,431
BEGIN DESCRIPTION:
Stream0161 17.0
END DESCRIPTION:
XS GIS Cut Line= 3
      1806074.95     13939124.99      1805974.58     13939111.29
      1805509.08     13939130.58
#Sta/Elev= 30
  4898.8 2046.10  4929.0 2043.76  4949.2 2040.95  4969.4 2037.03  4979.5 2034.00
  4997.4 2029.64  5002.4 2029.64  5009.7 2025.88  5017.2 2024.17  5017.6 2023.67
  5021.8 2023.67  5022.1 2024.17  5039.7 2026.60  5049.7 2026.57  5059.7 2025.58
  5069.7 2026.25  5079.8 2028.90  5089.8 2030.22  5109.8 2031.44  5159.8 2036.16
  5189.8 2037.69  5207.7 2039.90  5219.9 2040.59  5239.9 2043.79  5279.9 2048.44
  5309.9 2050.12  5340.0 2052.56  5410.0 2055.03  5460.1 2058.04  5466.0 2058.87
#Mann=3,-1,0
  4898.8     0.1       0  5017.2    0.05       0  5022.1     0.1       0
Bank Sta=5017.2,5022.1
Exp/Cntr=0.3,0.1

Type RM Length L Ch R = 1,7419,450,450,450
BEGIN DESCRIPTION:
Stream0161 16.0
END DESCRIPTION:
XS GIS Cut Line= 3
      1806125.00     13938825.00      1805925.00     13938725.00
      1805513.49     13938582.16
#Sta/Elev= 30
  4776.0 2039.76  4829.1 2037.34  4843.1 2036.26  4851.5 2034.63  4879.4 2033.10
  4924.1 2027.24  4932.5 2025.25  4940.9 2024.26  4946.5 2024.76  4963.3 2022.60
  5012.7 2022.02  5013.1 2021.52  5017.7 2022.02  5041.0 2028.90  5046.3 2029.13
  5052.5 2032.11  5072.1 2035.49  5077.4 2035.70  5084.3 2037.59  5103.3 2040.66
  5108.5 2040.74  5147.8 2048.18  5179.6 2051.33  5243.1 2054.16  5264.2 2056.04
  5274.8 2055.95  5306.6 2059.19  5315.8 2058.80  5378.1 2061.78  5435.2 2065.58
#Mann=3,-1,0
  4776.0    0.07       0  5012.7    0.05       0  5017.7    0.07       0
Bank Sta=5012.7,5017.7
Exp/Cntr=0.3,0.1

Type RM Length L Ch R = 1,6969,410,410,410
BEGIN DESCRIPTION:
Stream0161 15.0
END DESCRIPTION:
XS GIS Cut Line= 3
      1806325.02     13938625.03      1806075.00     13938325.00
      1805974.98     13938224.98
#Sta/Elev= 30
  4604.2 2040.56  4640.0 2038.90  4753.3 2031.28  4765.0 2030.92  4796.2 2029.06
  4802.7 2028.12  4810.6 2028.14  4845.7 2026.07  4888.7 2024.79  4909.5 2023.46
  4938.1 2023.16  4958.9 2020.60  4966.8 2020.73  4973.3 2018.80  4981.1 2018.00
  4998.3 2017.96  5008.9 2016.57  5020.5 2016.20  5020.9 2015.70  5025.2 2015.70
  5025.5 2016.20  5030.1 2017.59  5037.2 2025.18  5051.3 2032.77  5065.5 2035.86
  5093.7 2038.54  5107.9 2040.72  5122.0 2042.02  5132.6 2043.97  5136.2 2043.97
#Mann=4,-1,0
  4604.2    0.07       0  4765.0     0.1       0  5020.5    0.05       0
  5025.5     0.1       0
Bank Sta=5020.5,5025.5
Exp/Cntr=0.3,0.1

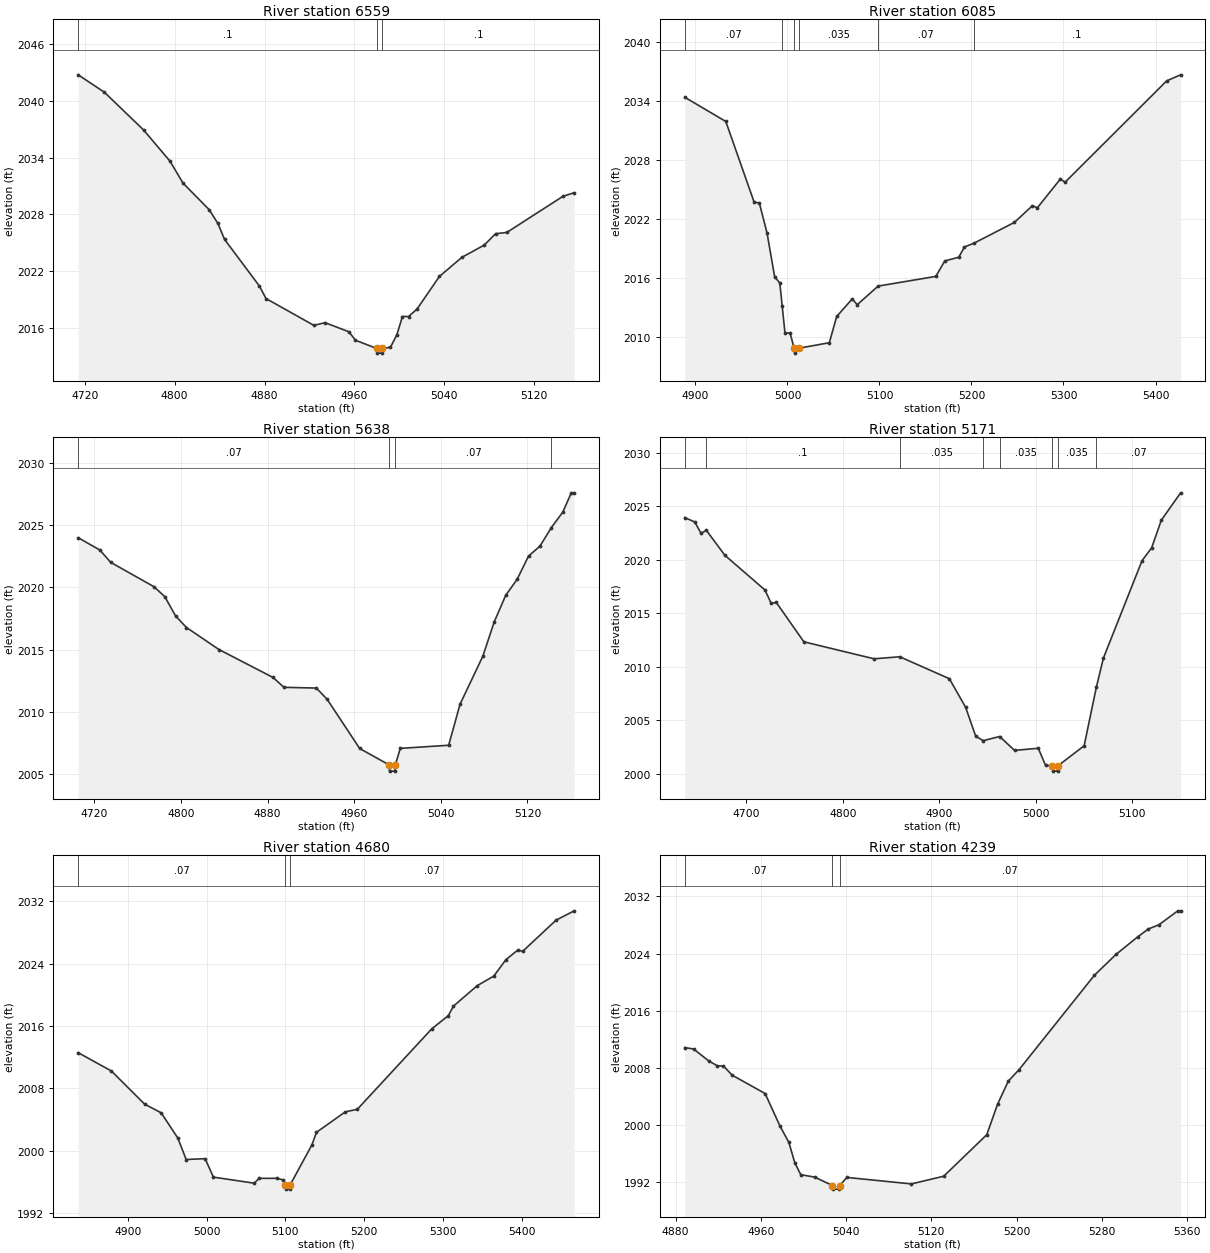
Type RM Length L Ch R = 1,6559,474,474,474
BEGIN DESCRIPTION:
Stream0161 14.0
END DESCRIPTION:
XS GIS Cut Line= 3
      1806575.03     13938175.02      1806325.00     13938025.00
      1806174.98     13938025.00
#Sta/Elev= 30
  4714.1 2042.75  4737.5 2040.90  4772.4 2036.91  4795.8 2033.63  4807.4 2031.31
  4830.7 2028.50  4838.5 2027.04  4844.4 2025.36  4875.5 2020.42  4881.3 2019.11
  4924.0 2016.27  4933.8 2016.56  4955.1 2015.60  4961.0 2014.70  4979.8 2013.84
  4980.2 2013.34  4984.6 2013.34  4985.0 2013.84  4992.1 2013.95  4997.9 2015.30
  5002.8 2017.21  5008.2 2017.21  5015.7 2017.98  5035.7 2021.44  5055.7 2023.46
  5075.7 2024.76  5085.7 2025.96  5095.7 2026.09  5145.7 2029.91  5155.7 2030.29
#Mann=3,-1,0
  4714.1     0.1       0  4979.8    0.05       0  4985.0     0.1       0
Bank Sta=4979.8,4985
Exp/Cntr=0.3,0.1

Type RM Length L Ch R = 1,6085,447,447,447
BEGIN DESCRIPTION:
Stream0161 13.0
END DESCRIPTION:
XS GIS Cut Line= 3
      1806675.01     13937725.01      1806575.00     13937675.00
      1806175.01     13937525.01
#Sta/Elev= 30
  4888.3 2034.39  4933.0 2031.92  4963.8 2023.70  4969.4 2023.63  4977.8 2020.57
  4986.1 2016.10  4991.7 2015.47  4994.3 2013.11  4997.3 2010.39  5002.8 2010.39
  5007.3 2008.83  5007.7 2008.33  5012.5 2008.83  5045.5 2009.39  5053.5 2012.06
  5070.4 2013.85  5075.8 2013.26  5098.6 2015.16  5161.2 2016.14  5171.0 2017.72
  5186.1 2018.09  5192.4 2019.14  5202.6 2019.52  5246.6 2021.64  5266.2 2023.34
  5271.6 2023.13  5296.5 2026.05  5301.8 2025.74  5412.2 2036.06  5427.3 2036.67
#Mann=6,-1,0
  4888.3    0.07       0  4994.3   0.035       0  5007.3   0.035       0
  5012.5   0.035       0  5098.6    0.07       0  5202.6     0.1       0
Bank Sta=5007.3,5012.5
Exp/Cntr=0.3,0.1

Type RM Length L Ch R = 1,5638,467,467,467
BEGIN DESCRIPTION:
Stream0161 12.0
END DESCRIPTION:
XS GIS Cut Line= 3
      1806725.00     13937275.00      1806425.00     13937275.00
      1806275.02     13937324.99
#Sta/Elev= 30
  4705.0 2024.00  4725.0 2023.01  4735.0 2022.02  4775.0 2020.06  4785.0 2019.26
  4795.0 2017.70  4805.0 2016.78  4835.0 2015.01  4885.0 2012.76  4895.0 2011.97
  4925.0 2011.91  4935.0 2011.00  4965.0 2007.05  4992.2 2005.73  4992.6 2005.23
  4997.4 2005.23  4997.9 2005.73  5002.5 2007.06  5047.2 2007.31  5057.7 2010.61
  5078.8 2014.48  5089.3 2017.24  5099.9 2019.37  5110.4 2020.65  5121.0 2022.53
  5131.5 2023.32  5142.1 2024.82  5152.6 2026.06  5160.5 2027.61  5163.1 2027.61
#Mann=4,-1,0
  4705.0    0.07       0  4992.2    0.05       0  4997.9    0.07       0
  5142.1     0.1       0
Bank Sta=4992.2,4997.9
Exp/Cntr=0.3,0.1

Type RM Length L Ch R = 1,5171,491,491,491
BEGIN DESCRIPTION:
Stream0161 11.0
END DESCRIPTION:
XS GIS Cut Line= 3
      1806724.99     13936725.00      1806375.00     13936825.00
      1806224.99     13936825.00
#Sta/Elev= 30
  4636.0 2023.95  4646.4 2023.55  4652.9 2022.49  4658.5 2022.76  4677.6 2020.43
  4719.2 2017.18  4725.7 2015.92  4730.9 2016.02  4759.5 2012.33  4832.3 2010.74
  4858.9 2010.93  4910.3 2008.88  4927.2 2006.20  4937.6 2003.50  4945.4 2003.08
  4962.4 2003.47  4977.9 2002.17  5002.5 2002.37  5010.0 2000.77  5017.1 2000.73
  5017.6 2000.23  5022.4 2000.23  5022.9 2000.73  5050.0 2002.60  5062.7 2008.09
  5070.0 2010.81  5110.0 2019.92  5120.0 2021.13  5130.0 2023.71  5150.0 2026.27
#Mann=8,-1,0
  4636.0    0.07       0  4658.5     0.1       0  4858.9   0.035       0
  4945.4    0.07       0  4962.4   0.035       0  5017.1   0.035       0
  5022.9   0.035       0  5062.7    0.07       0
Bank Sta=5017.1,5022.9
Exp/Cntr=0.3,0.1

Type RM Length L Ch R = 1,4680,441,441,441
BEGIN DESCRIPTION:
Stream0161 10.0
END DESCRIPTION:
XS GIS Cut Line= 3
      1806625.02     13936425.01      1806475.00     13936375.00
      1806225.02     13935975.03
#Sta/Elev= 30
  4836.9 2012.58  4879.1 2010.22  4921.2 2005.98  4942.3 2004.86  4963.4 2001.62
  4974.0 1998.87  4998.0 1998.98  5008.6 1996.61  5060.5 1995.83  5066.4 1996.45
  5089.4 1996.46  5097.0 1996.25  5100.0 1995.57  5100.5 1995.07  5105.4 1995.07
  5105.8 1995.57  5133.6 2000.73  5139.5 2002.36  5176.0 2004.98  5191.4 2005.32
  5285.7 2015.62  5306.9 2017.33  5313.4 2018.55  5343.5 2021.17  5364.7 2022.41
  5380.1 2024.52  5395.4 2025.76  5401.3 2025.58  5443.7 2029.58  5466.7 2030.78
#Mann=3,-1,0
  4836.9    0.07       0  5100.0    0.05       0  5105.8    0.07       0
Bank Sta=5100,5105.8
Exp/Cntr=0.3,0.1

Type RM Length L Ch R = 1,4239,427,427,427
BEGIN DESCRIPTION:
Stream0161 9.0
END DESCRIPTION:
XS GIS Cut Line= 3
      1806725.00     13936125.00      1806675.00     13936025.00
      1806624.99     13935674.96
#Sta/Elev= 30
  4888.5 2010.82  4896.9 2010.62  4910.9 2008.97  4919.2 2008.26  4924.8 2008.24
  4933.2 2006.94  4964.0 2004.38  4977.9 1999.83  4986.3 1997.52  4991.9 1994.64
  4997.5 1993.00  5010.4 1992.67  5027.2 1991.48  5027.7 1990.98  5033.5 1990.98
  5034.0 1991.48  5040.7 1992.62  5101.3 1991.71  5131.6 1992.79  5172.0 1998.61
  5182.1 2002.87  5192.2 2006.12  5202.3 2007.73  5273.0 2020.96  5293.2 2023.87
  5313.5 2026.33  5323.6 2027.44  5333.7 2028.05  5351.3 2029.99  5353.9 2029.99
#Mann=3,-1,0
  4888.5    0.07       0  5027.2    0.05       0  5034.0    0.07       0
Bank Sta=5027.2,5034
Exp/Cntr=0.3,0.1

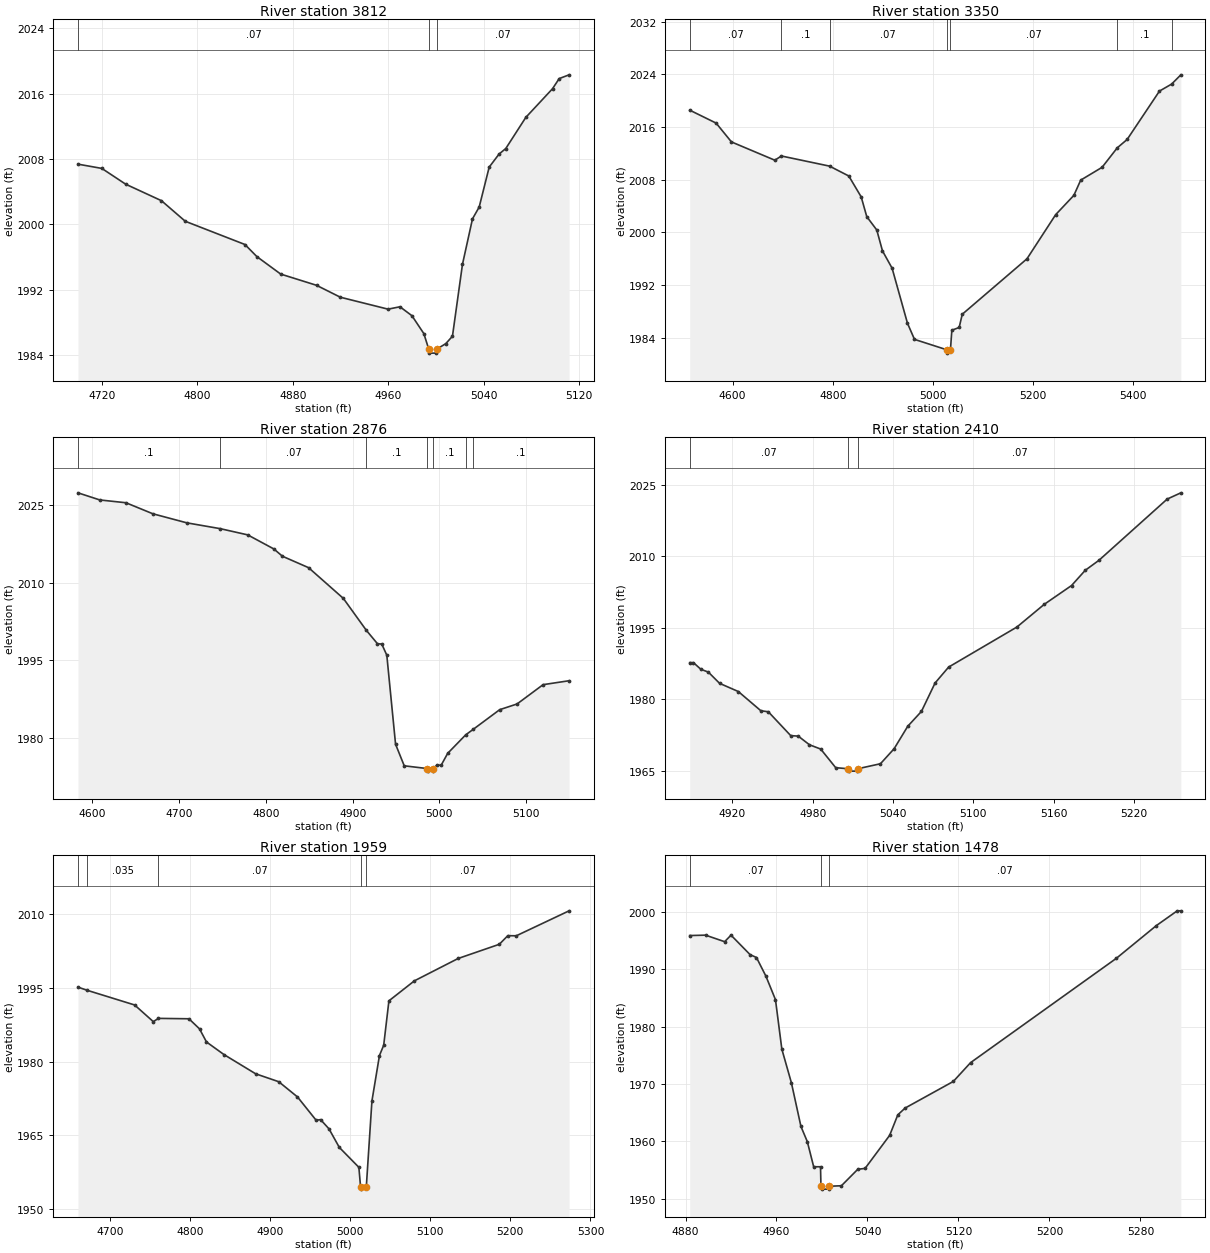
Type RM Length L Ch R = 1,3812,462,462,462
BEGIN DESCRIPTION:
Stream0161 8.0
END DESCRIPTION:
XS GIS Cut Line= 3
      1806925.00     13936025.04      1806925.00     13935725.00
      1806875.02     13935625.04
#Sta/Elev= 30
  4699.9 2007.37  4719.9 2006.85  4739.9 2004.92  4769.9 2002.90  4789.9 2000.38
  4839.9 1997.54  4849.9 1996.06  4869.9 1993.92  4899.9 1992.55  4919.9 1991.09
  4959.9 1989.63  4969.9 1989.92  4979.9 1988.83  4989.9 1986.64  4994.0 1984.75
  4994.5 1984.25  5000.4 1984.25  5000.9 1984.75  5008.3 1985.41  5013.9 1986.32
  5022.3 1995.12  5030.7 2000.68  5036.3 2002.12  5044.7 2007.01  5053.0 2008.61
  5058.6 2009.28  5075.4 2013.09  5097.8 2016.60  5103.4 2017.84  5111.7 2018.30
#Mann=3,-1,0
  4699.9    0.07       0  4994.0    0.05       0  5000.9    0.07       0
Bank Sta=4994,5000.9
Exp/Cntr=0.3,0.1

Type RM Length L Ch R = 1,3350,474,474,474
BEGIN DESCRIPTION:
Stream0161 7.0
END DESCRIPTION:
XS GIS Cut Line= 3
      1807538.97     13936126.85      1807375.00     13935675.00
      1806974.98     13935374.99
#Sta/Elev= 30
  4514.4 2018.58  4567.1 2016.61  4597.7 2013.75  4684.3 2010.97  4697.5 2011.61
  4793.6 2010.07  4832.0 2008.57  4856.8 2005.39  4867.9 2002.39  4887.9 2000.36
  4899.3 1997.18  4918.5 1994.55  4949.2 1986.18  4963.2 1983.73  5028.1 1982.14
  5028.6 1981.64  5035.0 1982.14  5037.8 1985.12  5052.4 1985.54  5058.6 1987.55
  5187.8 1995.98  5245.1 2002.69  5281.5 2005.63  5295.1 2007.94  5337.8 2009.89
  5368.1 2012.85  5387.8 2014.12  5452.4 2021.48  5476.6 2022.54  5495.1 2023.95
#Mann=7,-1,0
  4514.4    0.07       0  4697.5     0.1       0  4793.6    0.07       0
  5028.1    0.05       0  5035.0    0.07       0  5368.1     0.1       0
  5476.6    0.07       0
Bank Sta=5028.1,5035
Exp/Cntr=0.3,0.1

Type RM Length L Ch R = 1,2876,466,466,466
BEGIN DESCRIPTION:
Stream0161 6.0
END DESCRIPTION:
XS GIS Cut Line= 3
      1807990.14     13935406.17      1807575.00     13935375.00
      1807425.00     13935375.00
#Sta/Elev= 30
  4583.3 2027.44  4608.5 2026.06  4638.6 2025.52  4669.7 2023.38  4708.8 2021.63
  4747.4 2020.50  4779.0 2019.30  4809.1 2016.58  4819.1 2015.16  4849.2 2012.95
  4889.3 2007.00  4915.8 2000.82  4928.6 1998.23  4933.6 1998.16  4939.4 1996.01
  4949.5 1978.77  4959.5 1974.59  4986.0 1974.06  4986.5 1973.56  4992.6 1973.56
  4993.1 1974.06  4997.1 1974.71  5002.1 1974.71  5009.6 1977.00  5030.4 1980.59
  5038.8 1981.62  5069.6 1985.46  5089.6 1986.56  5119.6 1990.30  5149.6 1991.06
#Mann=7,-1,0
  4583.3     0.1       0  4747.4    0.07       0  4915.8     0.1       0
  4986.0    0.05       0  4993.1     0.1       0  5030.4    0.07       0
  5038.8     0.1       0
Bank Sta=4986,4993.1
Exp/Cntr=0.3,0.1

Type RM Length L Ch R = 1,2410,451,451,451
BEGIN DESCRIPTION:
Stream0161 5.0
END DESCRIPTION:
XS GIS Cut Line= 3
      1807624.97     13934974.98      1807525.00     13934925.00
      1807275.02     13934875.00
#Sta/Elev= 30
  4888.2 1987.66  4891.0 1987.66  4896.5 1986.27  4902.1 1985.68  4910.5 1983.32
  4924.5 1981.60  4941.3 1977.57  4946.9 1977.35  4963.6 1972.35  4969.2 1972.25
  4977.6 1970.43  4986.0 1969.53  4997.2 1965.62  5006.6 1965.40  5007.1 1964.90
  5013.2 1964.90  5013.7 1965.40  5030.6 1966.45  5040.8 1969.60  5051.0 1974.32
  5061.2 1977.43  5071.4 1983.40  5081.5 1986.73  5132.5 1995.14  5152.9 1999.90
  5173.3 2003.85  5183.5 2007.04  5193.7 2009.13  5244.7 2021.99  5254.9 2023.30
#Mann=3,-1,0
  4888.2    0.07       0  5006.6    0.05       0  5013.7    0.07       0
Bank Sta=5006.6,5013.7
Exp/Cntr=0.3,0.1

Type RM Length L Ch R = 1,1959,481,481,481
BEGIN DESCRIPTION:
Stream0161 4.0
END DESCRIPTION:
XS GIS Cut Line= 3
      1807859.64     13934881.87      1807725.00     13934575.00
      1807632.89     13934312.82
#Sta/Elev= 30
  4660.3 1995.19  4671.9 1994.54  4731.0 1991.56  4754.3 1988.17  4760.8 1988.83
  4798.8 1988.75  4812.0 1986.70  4820.7 1984.03  4842.5 1981.47  4882.1 1977.55
  4910.9 1975.94  4934.3 1972.84  4957.6 1968.09  4963.1 1968.23  4973.6 1966.35
  4986.5 1962.57  5010.9 1958.52  5013.0 1954.58  5013.5 1954.08  5020.2 1954.58
  5027.2 1972.02  5036.6 1981.27  5041.9 1983.37  5048.4 1992.40  5080.2 1996.47
  5134.8 2001.02  5186.2 2003.91  5196.8 2005.66  5207.4 2005.64  5273.3 2010.72
#Mann=5,-1,0
  4660.3    0.07       0  4671.9   0.035       0  4760.8    0.07       0
  5013.0    0.05       0  5020.2    0.07       0
Bank Sta=5013,5020.2
Exp/Cntr=0.3,0.1

Type RM Length L Ch R = 1,1478,469,469,469
BEGIN DESCRIPTION:
Stream0161 3.0
END DESCRIPTION:
XS GIS Cut Line= 3
      1808224.98     13934574.96      1808175.00     13934475.00
      1807975.01     13934225.01
#Sta/Elev= 30
  4883.7 1995.89  4897.6 1995.96  4914.4 1994.82  4920.0 1995.96  4936.8 1992.56
  4942.4 1992.06  4950.7 1988.81  4959.1 1984.72  4964.7 1976.09  4973.1 1970.23
  4981.5 1962.61  4987.1 1959.97  4992.7 1955.59  4998.7 1955.59  4999.1 1952.19
  4999.6 1951.69  5005.8 1951.69  5006.3 1952.19  5017.1 1952.28  5031.5 1955.15
  5037.9 1955.30  5059.5 1961.06  5066.7 1964.64  5073.1 1965.82  5115.5 1970.46
  5130.7 1973.74  5258.8 1991.91  5294.0 1997.62  5312.4 2000.20  5315.6 2000.20
#Mann=3,-1,0
  4883.7    0.07       0  4999.1    0.05       0  5006.3    0.07       0
Bank Sta=4999.1,5006.3
Exp/Cntr=0.3,0.1

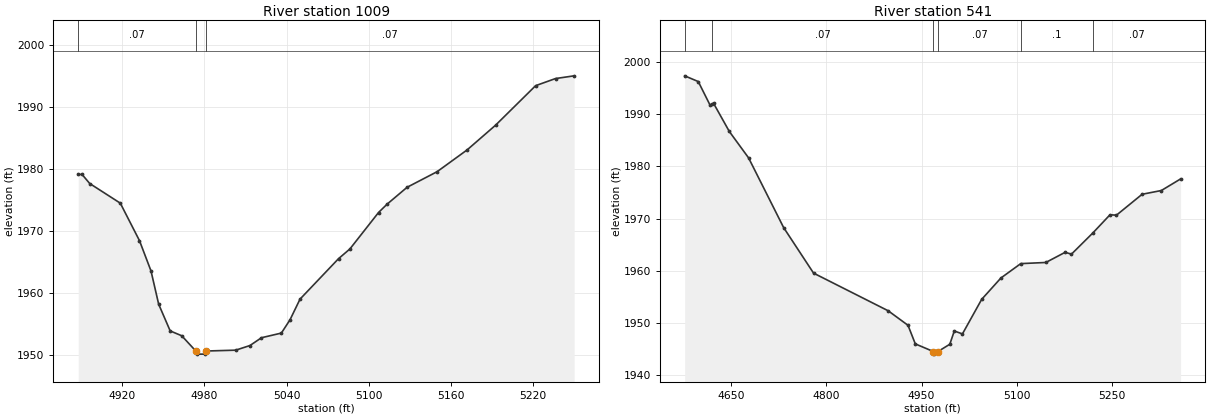
Type RM Length L Ch R = 1,1009,468,468,468
BEGIN DESCRIPTION:
Stream0161 2.0
END DESCRIPTION:
XS GIS Cut Line= 3
      1808524.99     13934224.99      1808475.00     13934125.00
      1808274.99     13933974.99
#Sta/Elev= 30
  4888.0 1979.14  4890.8 1979.14  4896.4 1977.67  4918.7 1974.50  4932.7 1968.44
  4941.1 1963.55  4946.7 1958.17  4955.1 1953.86  4963.5 1953.08  4973.8 1950.61
  4974.3 1950.11  4980.6 1950.11  4981.1 1950.61  5002.9 1950.75  5013.3 1951.50
  5021.7 1952.76  5036.2 1953.51  5042.5 1955.65  5049.8 1958.99  5077.9 1965.53
  5086.2 1967.10  5107.1 1972.99  5113.3 1974.33  5127.9 1977.06  5149.8 1979.58
  5171.7 1983.10  5192.5 1987.10  5221.7 1993.48  5236.2 1994.63  5249.8 1995.07
#Mann=3,-1,0
  4888.0    0.07       0  4973.8    0.05       0  4981.1    0.07       0
Bank Sta=4973.8,4981.1
Exp/Cntr=0.3,0.1

Type RM Length L Ch R = 1,541,0,0,0
BEGIN DESCRIPTION:
Stream0161 1.0
END DESCRIPTION:
XS GIS Cut Line= 3
      1808925.00     13934175.01      1808775.00     13933775.00
      1808424.97     13933725.00
#Sta/Elev= 30
  4577.1 1997.34  4598.5 1996.24  4617.2 1991.69  4619.9 1991.89  4622.5 1992.09
  4647.4 1986.68  4677.7 1981.63  4732.9 1968.28  4780.0 1959.56  4897.5 1952.35
  4928.7 1949.57  4940.2 1946.01  4968.6 1944.55  4969.1 1944.05  4975.9 1944.55
  4994.5 1945.94  5001.6 1948.48  5014.4 1947.92  5044.7 1954.54  5075.0 1958.63
  5106.2 1961.38  5145.7 1961.60  5176.0 1963.54  5186.1 1963.20  5219.7 1967.25
  5246.7 1970.73  5256.9 1970.66  5297.3 1974.66  5327.6 1975.38  5357.9 1977.60
#Mann=6,-1,0
  4577.1     0.1       0  4619.9    0.07       0  4968.6    0.05       0
  4975.9    0.07       0  5106.2     0.1       0  5219.7    0.07       0
Bank Sta=4968.6,4975.9
Exp/Cntr=0.3,0.1

Chan Stop Cuts=-1