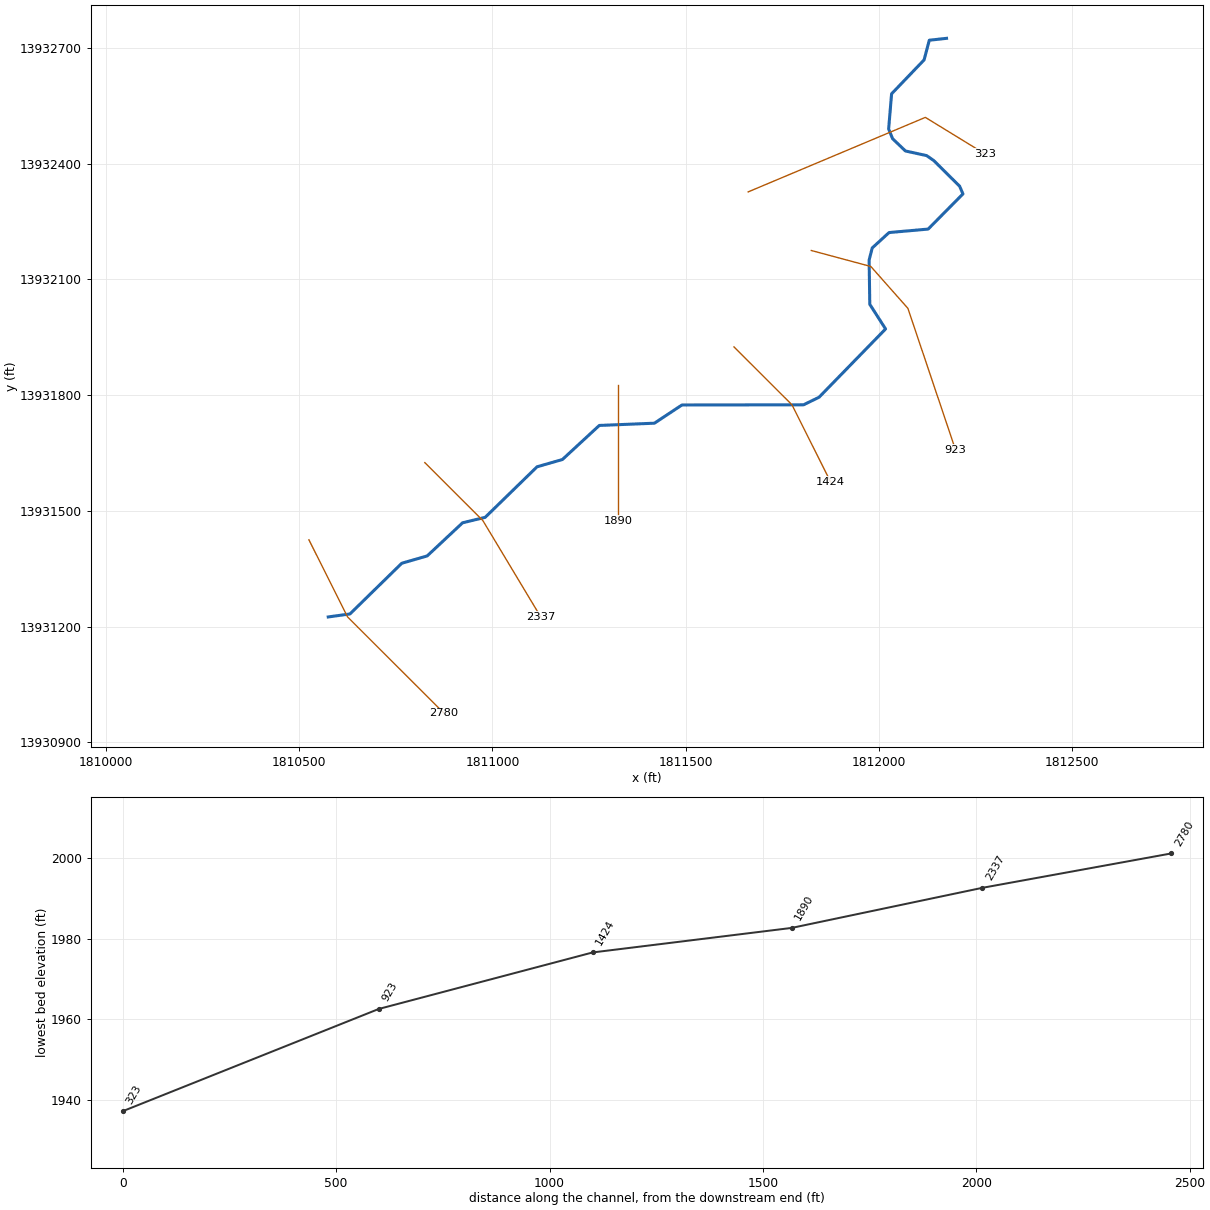
--- Stream0163.prj (project) ---

Proj Title=Stream0163 Base Level Engineering
Current Plan=p01
Default Exp/Contr=0.3,0.1
English Units
Geom File=g01
Flow File=f01
Plan File=p01
BEGIN DESCRIPTION:
Stream0163
END DESCRIPTION:

--- Stream0163.p01 (plan) ---

Plan Title=Multiple Run
Short Identifier=Multiple
Geom File=g01
Flow File=f01
Subcritical Flow
K Sum by GR= 0
Std Step Tol= 0.01
Critical Tol= 0.01
Num of Std Step Trials= 20
Max Error Tol= 0.3
Flow Tol Ratio= 0.001
Split Flow NTrial= 30
Split Flow Tol= 0.02
Split Flow Ratio= 0.02
Log Output Level= 0
Friction Slope Method= 1
Unsteady Friction Slope Method= 2
Unsteady Bridges Friction Slope Method= 1
Parabolic Critical Depth
Global Vel Dist=  1 , 1 , 1
Global Log Level= 0
CheckData=True
Encroach Param= -1, 0, 0, 0
BEGIN DESCRIPTION:
Multiple Run
END DESCRIPTION:

--- Stream0163.f01 (steady flow) ---

Flow Title=Multiple
Number of Profiles=7
Profile Names=10-year,25-year,50-year,1pct_min,100-year,1pct_plu,500-year
River Rch & RM= Stream0163,Reach-1,2780
     725    1223    1692    1135    2264    4518    4003
Boundary for River Rch & Prof#=Stream0163,Reach-1,1
Up Type=0
Dn Type=3
Dn Slope=0.005
Boundary for River Rch & Prof#=Stream0163,Reach-1,2
Up Type=0
Dn Type=3
Dn Slope=0.005
Boundary for River Rch & Prof#=Stream0163,Reach-1,3
Up Type=0
Dn Type=3
Dn Slope=0.005
Boundary for River Rch & Prof#=Stream0163,Reach-1,4
Up Type=0
Dn Type=3
Dn Slope=0.005
Boundary for River Rch & Prof#=Stream0163,Reach-1,5
Up Type=0
Dn Type=3
Dn Slope=0.005
Boundary for River Rch & Prof#=Stream0163,Reach-1,6
Up Type=0
Dn Type=3
Dn Slope=0.005
Boundary for River Rch & Prof#=Stream0163,Reach-1,7
Up Type=0
Dn Type=3
Dn Slope=0.005

--- Stream0163.g01 (geometry) ---

Geom Title=Existing Conditions

River Reach=Stream0163,Reach-1
Reach XY= 30
      1810575.00     13931225.00      1810631.21     13931232.76
      1810765.32     13931364.22      1810831.04     13931383.18
      1810922.72     13931469.13      1810981.05     13931483.16
      1811115.32     13931614.22      1811181.04     13931633.18
      1811276.47     13931721.45      1811419.06     13931727.27
      1811490.22     13931774.48      1811805.02     13931774.96
      1811845.16     13931794.60      1812017.21     13931971.58
      1811976.38     13932035.44      1811974.64     13932150.21
      1811982.67     13932181.52      1812026.25     13932221.49
      1812127.45     13932230.53      1812217.42     13932321.66
      1812208.82     13932341.70      1812141.73     13932408.34
      1812123.35     13932421.01      1812068.62     13932433.02
      1812035.30     13932464.90      1812025.18     13932490.09
      1812032.77     13932581.16      1812116.92     13932669.11
      1812130.32     13932720.08      1812175.00     13932725.00

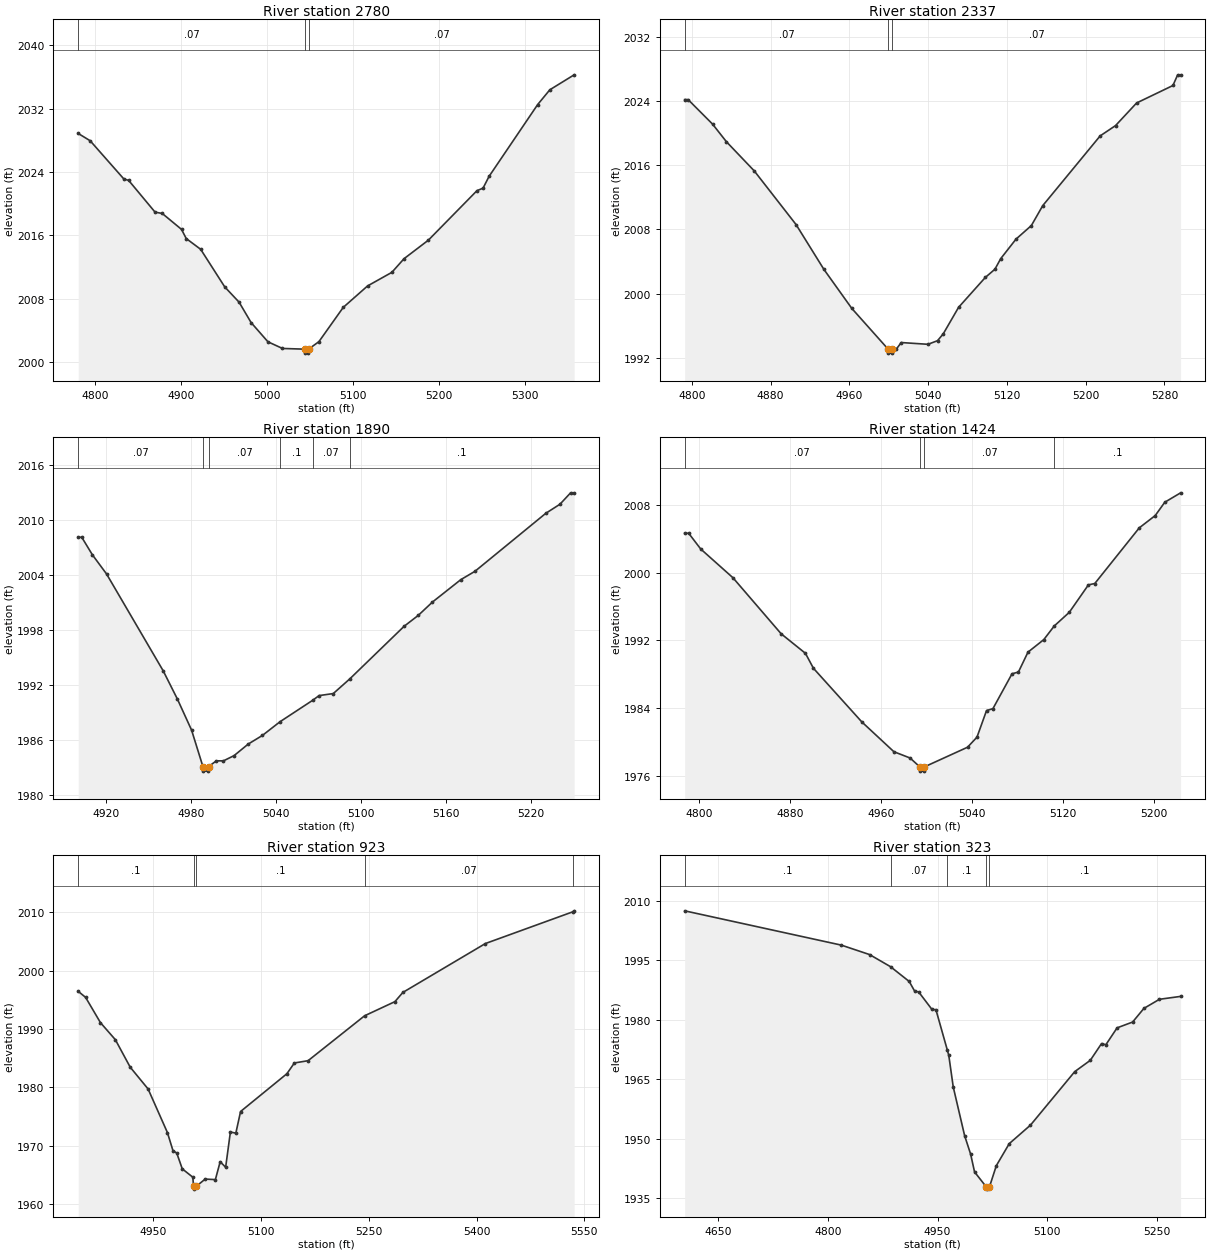
Type RM Length L Ch R = 1,2780,443,443,443
BEGIN DESCRIPTION:
Stream0163 6.0
END DESCRIPTION:
XS GIS Cut Line= 3
      1810525.02     13931424.97      1810625.00     13931225.00
      1810874.98     13930975.02
#Sta/Elev= 30
  4780.0 2028.86  4793.9 2027.94  4833.1 2023.11  4838.7 2022.93  4869.4 2018.92
  4877.8 2018.75  4900.2 2016.74  4905.7 2015.58  4922.5 2014.22  4950.5 2009.47
  4967.2 2007.54  4981.2 2004.96  5000.8 2002.53  5017.7 2001.69  5044.0 2001.60
  5044.2 2001.10  5047.7 2001.10  5048.0 2001.60  5060.1 2002.55  5088.4 2006.88
  5116.7 2009.59  5145.0 2011.31  5159.1 2013.03  5187.4 2015.37  5244.0 2021.63
  5251.1 2021.95  5258.1 2023.44  5314.7 2032.52  5328.8 2034.38  5357.1 2036.27
#Mann=3,-1,0
  4780.0    0.07       0  5044.0    0.05       0  5048.0    0.07       0
Bank Sta=5044,5048
Exp/Cntr=0.3,0.1

Type RM Length L Ch R = 1,2337,447,447,447
BEGIN DESCRIPTION:
Stream0163 5.0
END DESCRIPTION:
XS GIS Cut Line= 3
      1810825.02     13931624.98      1810975.00     13931475.00
      1811125.02     13931224.96
#Sta/Elev= 30
  4792.7 2024.18  4796.2 2024.18  4821.0 2021.13  4835.1 2018.93  4863.4 2015.29
  4905.8 2008.61  4934.1 2003.02  4962.4 1998.16  4999.3 1993.08  4999.5 1992.58
  5003.0 1992.58  5003.3 1993.08  5007.7 1993.08  5012.6 1993.90  5039.8 1993.68
  5049.5 1994.13  5055.3 1994.98  5070.9 1998.29  5098.1 2002.02  5107.8 2003.04
  5113.7 2004.36  5129.2 2006.79  5144.8 2008.48  5156.4 2010.97  5214.7 2019.66
  5230.3 2020.94  5251.7 2023.76  5288.6 2025.94  5293.4 2027.27  5296.4 2027.27
#Mann=3,-1,0
  4792.7    0.07       0  4999.3    0.05       0  5003.3    0.07       0
Bank Sta=4999.3,5003.3
Exp/Cntr=0.3,0.1

Type RM Length L Ch R = 1,1890,466,466,466
BEGIN DESCRIPTION:
Stream0163 4.0
END DESCRIPTION:
XS GIS Cut Line= 3
      1811325.00     13931825.02      1811325.00     13931725.00
      1811325.00     13931475.02
#Sta/Elev= 30
  4900.3 2008.13  4902.8 2008.13  4910.3 2006.22  4920.3 2004.13  4960.3 1993.57
  4970.3 1990.50  4980.3 1987.12  4988.3 1983.15  4988.6 1982.65  4992.1 1982.65
  4992.3 1983.15  4997.8 1983.77  5002.8 1983.77  5010.3 1984.34  5020.3 1985.60
  5030.3 1986.54  5042.8 1988.04  5065.7 1990.36  5070.3 1990.88  5080.3 1991.10
  5091.9 1992.69  5130.3 1998.43  5140.3 1999.62  5150.3 2001.07  5170.3 2003.51
  5180.3 2004.42  5230.3 2010.74  5240.3 2011.73  5247.8 2012.97  5250.3 2012.97
#Mann=6,-1,0
  4900.3    0.07       0  4988.3    0.05       0  4992.3    0.07       0
  5042.8     0.1       0  5065.7    0.07       0  5091.9     0.1       0
Bank Sta=4988.3,4992.3
Exp/Cntr=0.3,0.1

Type RM Length L Ch R = 1,1424,501,501,501
BEGIN DESCRIPTION:
Stream0163 3.0
END DESCRIPTION:
XS GIS Cut Line= 3
      1811625.01     13931924.99      1811775.00     13931775.00
      1811874.99     13931575.02
#Sta/Elev= 30
  4787.4 2004.65  4790.9 2004.65  4801.5 2002.79  4829.8 1999.40  4872.2 1992.78
  4893.5 1990.48  4900.5 1988.72  4943.0 1982.39  4971.2 1978.87  4985.4 1978.13
  4994.0 1977.08  4994.2 1976.58  4997.7 1976.58  4998.0 1977.08  5035.9 1979.40
  5044.2 1980.59  5052.6 1983.73  5058.2 1983.95  5075.0 1988.07  5080.6 1988.27
  5089.0 1990.62  5102.9 1992.10  5112.1 1993.71  5125.3 1995.32  5142.1 1998.56
  5147.7 1998.72  5186.8 2005.29  5200.8 2006.74  5209.2 2008.31  5223.1 2009.42
#Mann=4,-1,0
  4787.4    0.07       0  4994.0    0.05       0  4998.0    0.07       0
  5112.1     0.1       0
Bank Sta=4994,4998
Exp/Cntr=0.3,0.1

Type RM Length L Ch R = 1,923,600,600,600
BEGIN DESCRIPTION:
Stream0163 2.0
END DESCRIPTION:
XS GIS Cut Line= 4
      1811825.04     13932174.99      1811979.14     13932133.53
      1812075.00     13932025.00      1812198.02     13931658.90
#Sta/Elev= 30
  4845.3 1996.46  4855.6 1995.42  4876.3 1991.09  4897.0 1988.18  4917.7 1983.47
  4942.6 1979.74  4969.5 1972.28  4977.3 1969.16  4982.5 1968.77  4990.2 1966.06
  5004.9 1964.63  5005.9 1963.09  5006.1 1962.59  5009.9 1963.09  5022.1 1964.31
  5036.3 1964.22  5043.0 1967.29  5050.6 1966.33  5057.2 1972.36  5064.8 1972.18
  5071.4 1975.88  5135.9 1982.35  5146.3 1984.19  5165.4 1984.58  5244.1 1992.27
  5286.3 1994.69  5297.4 1996.27  5412.3 2004.64  5534.0 2010.07  5535.9 2010.24
#Mann=5,-1,0
  4845.3     0.1       0  5005.9    0.05       0  5009.9     0.1       0
  5244.1    0.07       0  5534.0     0.1       0
Bank Sta=5005.9,5009.9
Exp/Cntr=0.3,0.1

Type RM Length L Ch R = 1,323,0,0,0
BEGIN DESCRIPTION:
Stream0163 1.0
END DESCRIPTION:
XS GIS Cut Line= 3
      1811661.65     13932326.92      1812120.17     13932520.07
      1812274.98     13932425.01
#Sta/Elev= 30
  4603.7 2007.52  4818.3 1998.86  4856.9 1996.48  4885.6 1993.42  4911.2 1989.69
  4918.7 1987.23  4924.1 1987.06  4942.4 1982.62  4947.8 1982.56  4963.4 1972.37
  4965.4 1971.03  4971.5 1963.06  4987.1 1950.76  4995.3 1946.11  5000.7 1941.61
  5017.0 1937.77  5017.3 1937.27  5021.0 1937.77  5030.5 1943.19  5048.2 1948.75
  5077.3 1953.43  5137.9 1966.93  5159.2 1969.78  5174.6 1974.01  5180.5 1973.71
  5195.9 1977.98  5217.2 1979.45  5232.6 1982.89  5253.9 1985.19  5282.9 1985.92
#Mann=5,-1,0
  4603.7     0.1       0  4885.6    0.07       0  4963.4     0.1       0
  5017.0    0.05       0  5021.0     0.1       0
Bank Sta=5017,5021
Exp/Cntr=0.3,0.1

Chan Stop Cuts=-1