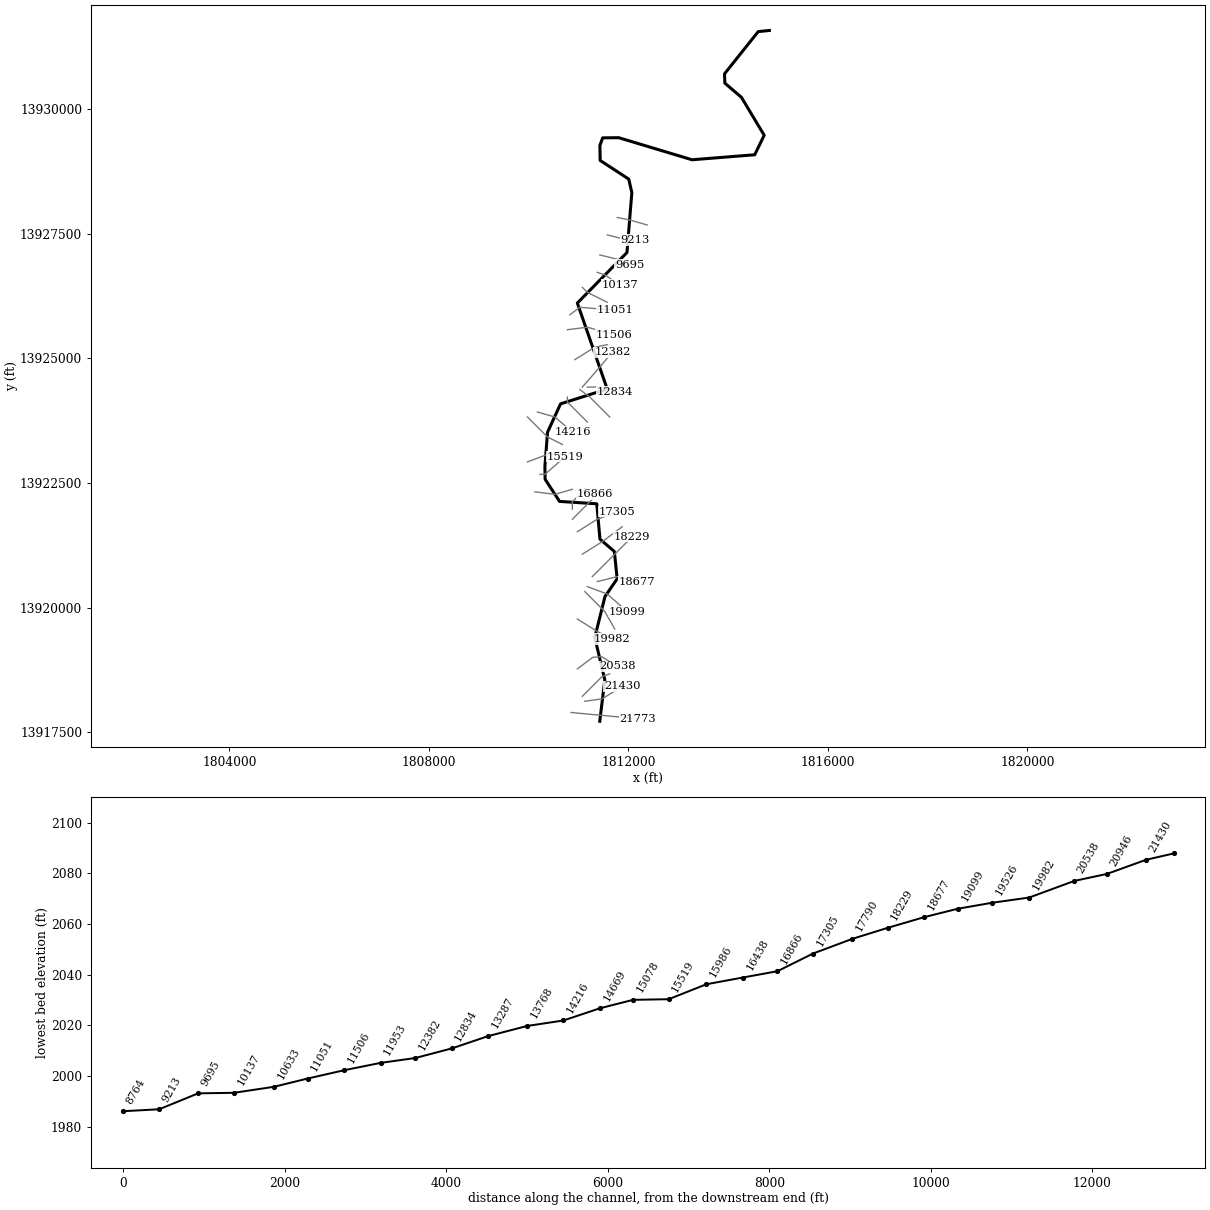
--- Stream0165.prj (project) ---

Proj Title=Stream0165 Base Level Engineering
Current Plan=p01
Default Exp/Contr=0.3,0.1
English Units
Geom File=g01
Flow File=f01
Plan File=p01
BEGIN DESCRIPTION:
Stream0165
END DESCRIPTION:

--- Stream0165.p01 (plan) ---

Plan Title=Multiple Run
Short Identifier=Multiple
Geom File=g01
Flow File=f01
Subcritical Flow
K Sum by GR= 0
Std Step Tol= 0.01
Critical Tol= 0.01
Num of Std Step Trials= 20
Max Error Tol= 0.3
Flow Tol Ratio= 0.001
Split Flow NTrial= 30
Split Flow Tol= 0.02
Split Flow Ratio= 0.02
Log Output Level= 0
Friction Slope Method= 1
Unsteady Friction Slope Method= 2
Unsteady Bridges Friction Slope Method= 1
Parabolic Critical Depth
Global Vel Dist=  1 , 1 , 1
Global Log Level= 0
CheckData=True
Encroach Param= -1, 0, 0, 0
BEGIN DESCRIPTION:
Multiple Run
END DESCRIPTION:

--- Stream0165.f01 (steady flow) ---

Flow Title=Multiple
Number of Profiles=7
Profile Names=10-year,25-year,50-year,1pct_min,100-year,1pct_plu,500-year
River Rch & RM= Stream0165,Reach-1,21773
    1741    3067    4365    2995    5976   11923   11087
River Rch & RM= Stream0165,Reach-1,15986
    3082    5573    8070    5623   11219   22385   21477
River Rch & RM= Stream0165,Reach-1,10137
    3256    5884    8517    5929   11830   23605   22610
River Rch & RM= Stream0165,Reach-1,3197
    3553    6442    9343    6515   13000   25938   24931
Boundary for River Rch & Prof#=Stream0165,Reach-1,1
Up Type=0
Dn Type=3
Dn Slope=0.005
Boundary for River Rch & Prof#=Stream0165,Reach-1,2
Up Type=0
Dn Type=3
Dn Slope=0.005
Boundary for River Rch & Prof#=Stream0165,Reach-1,3
Up Type=0
Dn Type=3
Dn Slope=0.005
Boundary for River Rch & Prof#=Stream0165,Reach-1,4
Up Type=0
Dn Type=3
Dn Slope=0.005
Boundary for River Rch & Prof#=Stream0165,Reach-1,5
Up Type=0
Dn Type=3
Dn Slope=0.005
Boundary for River Rch & Prof#=Stream0165,Reach-1,6
Up Type=0
Dn Type=3
Dn Slope=0.005
Boundary for River Rch & Prof#=Stream0165,Reach-1,7
Up Type=0
Dn Type=3
Dn Slope=0.005

--- Stream0165.g01 (geometry) ---

Geom Title=Existing Conditions

River Reach=Stream0165,Reach-1
Reach XY= 30
      1811425.00     13917725.00      1811525.28     13918554.82
      1811324.91     13919404.90      1811528.37     13920223.26
      1811772.94     13920580.86      1811717.21     13921128.43
      1811428.54     13921376.46      1811364.53     13922084.83
      1810618.65     13922132.43      1810328.75     13922576.55
      1810324.55     13922835.19      1810377.06     13923519.14
      1810638.44     13924088.64      1811573.97     13924385.43
      1810975.01     13926109.59      1811969.64     13927122.30
      1812067.67     13928324.90      1812005.40     13928595.17
      1811432.80     13928968.79      1811427.26     13929269.07
      1811482.97     13929422.07      1811804.97     13929424.93
      1813274.99     13928982.53      1814531.19     13929082.81
      1814721.25     13929473.45      1814264.61     13930235.10
      1813932.81     13930518.81      1813925.29     13930704.70
      1814601.16     13931552.15      1814825.00     13931575.00

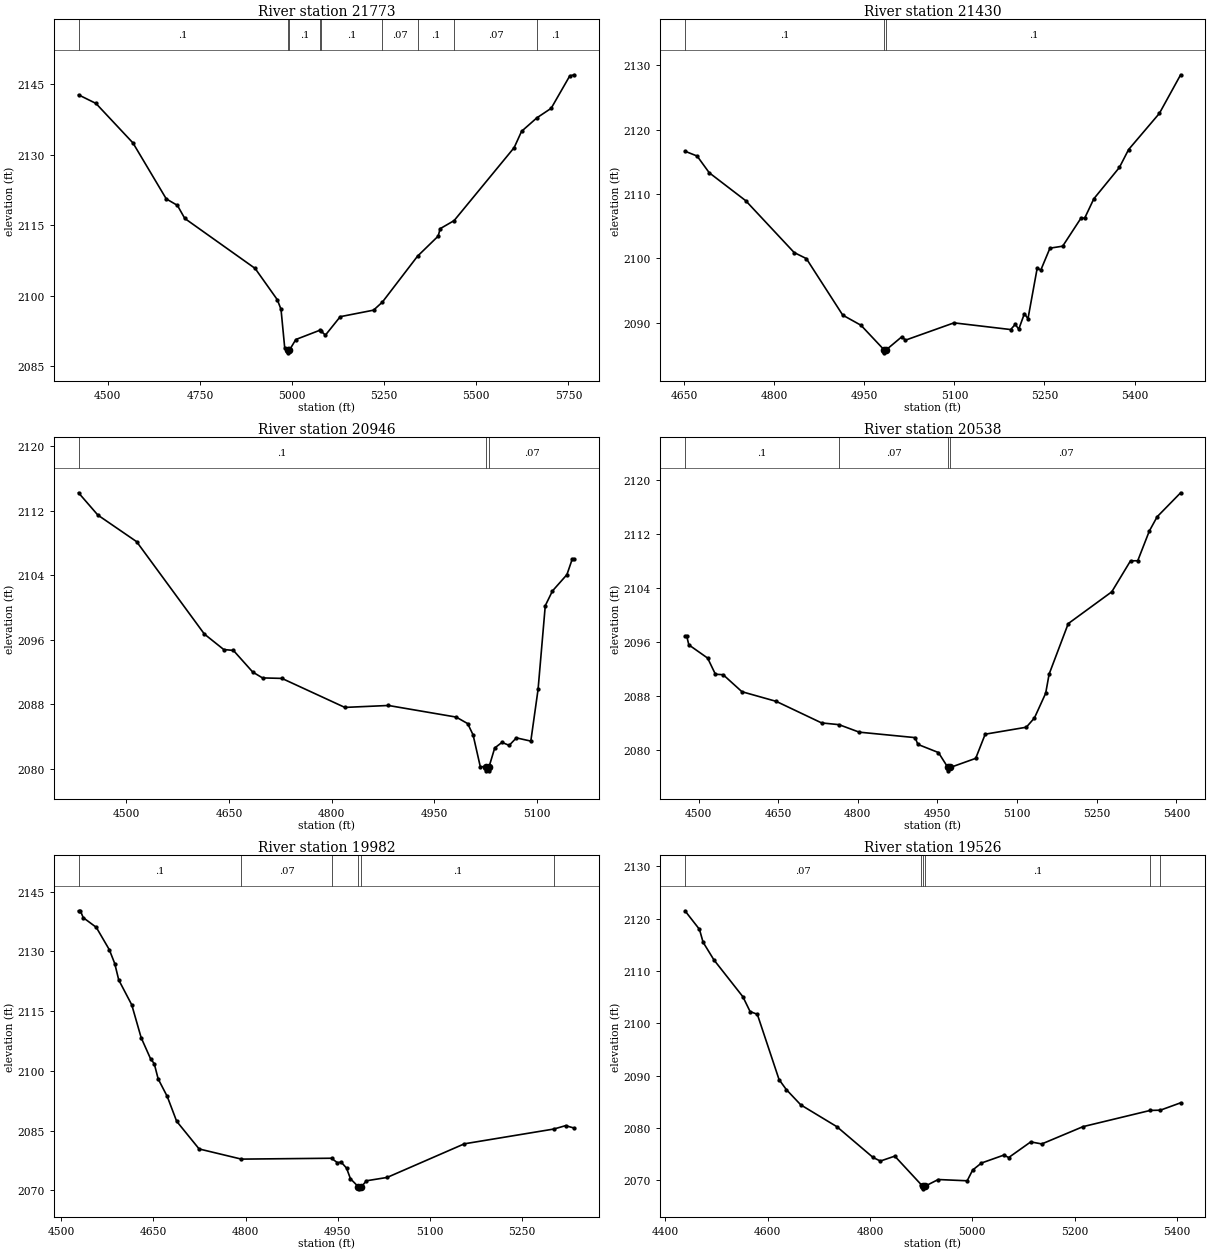
Type RM Length L Ch R = 1,21773,343,343,343
BEGIN DESCRIPTION:
Stream0165 46.0
END DESCRIPTION:
XS GIS Cut Line= 2
      1810847.89     13917900.50      1812187.09     13917775.74
#Sta/Elev= 30
  4420.4 2142.78  4467.7 2140.95  4568.1 2132.54  4658.5 2120.62  4688.7 2119.24
  4708.8 2116.45  4899.6 2105.81  4959.8 2099.15  4969.9 2097.11  4979.9 2088.93
  4987.9 2088.33  4988.1 2087.83  4992.1 2088.33  5010.1 2090.67  5075.9 2092.66
  5077.8 2092.52  5090.4 2091.60  5130.6 2095.53  5221.0 2096.92  5245.0 2098.64
  5340.3 2108.41  5396.4 2112.69  5401.7 2114.27  5439.6 2115.99  5602.6 2131.54
  5622.7 2135.01  5664.2 2137.88  5703.0 2139.91  5753.3 2146.79  5765.4 2147.05
#Mann=9,-1,0
  4420.4     0.1       0  4987.9    0.05       0  4992.1     0.1       0
  5075.9    0.07       0  5077.8     0.1       0  5245.0    0.07       0
  5340.3     0.1       0  5439.6    0.07       0  5664.2     0.1       0
Bank Sta=4987.9,4992.1
Exp/Cntr=0.3,0.1

Type RM Length L Ch R = 1,21430,484,484,484
BEGIN DESCRIPTION:
Stream0165 45.0
END DESCRIPTION:
XS GIS Cut Line= 3
      1811124.98     13918125.00      1811475.00     13918175.00
      1811875.02     13918425.01
#Sta/Elev= 30
  4651.4 2116.67  4671.6 2115.92  4691.8 2113.32  4752.4 2108.99  4833.2 2100.92
  4853.5 2099.98  4914.1 2091.19  4944.4 2089.62  4982.6 2085.83  4982.9 2085.33
  4986.9 2085.83  5012.6 2087.84  5018.5 2087.30  5099.3 2089.99  5193.7 2088.95
  5201.3 2089.75  5207.2 2089.01  5216.6 2091.43  5222.5 2090.62  5237.9 2098.51
  5243.8 2098.18  5259.1 2101.60  5280.3 2101.91  5311.0 2106.30  5316.9 2106.26
  5332.2 2109.28  5374.7 2114.14  5390.0 2116.92  5441.3 2122.55  5476.7 2128.55
#Mann=3,-1,0
  4651.4     0.1       0  4982.6    0.05       0  4986.9     0.1       0
Bank Sta=4982.6,4986.9
Exp/Cntr=0.3,0.1

Type RM Length L Ch R = 1,20946,408,408,408
BEGIN DESCRIPTION:
Stream0165 44.0
END DESCRIPTION:
XS GIS Cut Line= 3
      1811075.02     13918225.02      1811475.00     13918625.00
      1811625.03     13918675.01
#Sta/Elev= 30
  4430.2 2114.25  4458.5 2111.48  4515.0 2108.19  4614.0 2096.72  4642.3 2094.80
  4656.4 2094.69  4684.7 2092.00  4698.9 2091.28  4727.2 2091.22  4819.1 2087.62
  4882.7 2087.86  4981.7 2086.42  4998.5 2085.61  5006.4 2084.21  5016.9 2080.27
  5025.3 2080.25  5025.6 2079.75  5029.4 2079.75  5029.7 2080.25  5038.0 2082.59
  5048.6 2083.28  5059.1 2082.91  5069.6 2083.84  5090.7 2083.44  5101.3 2089.86
  5111.8 2100.24  5122.3 2102.07  5143.4 2104.09  5151.3 2106.05  5154.0 2106.05
#Mann=3,-1,0
  4430.2     0.1       0  5025.3    0.05       0  5029.7    0.07       0
Bank Sta=5025.3,5029.7
Exp/Cntr=0.3,0.1

Type RM Length L Ch R = 1,20538,556,556,556
BEGIN DESCRIPTION:
Stream0165 43.0
END DESCRIPTION:
XS GIS Cut Line= 4
      1810974.97     13918774.98      1811283.21     13919006.16
      1811462.85     13919020.09      1811775.02     13918824.99
#Sta/Elev= 30
  4474.4 2096.92  4477.6 2096.92  4481.7 2095.61  4517.1 2093.65  4531.7 2091.26
  4546.3 2091.19  4581.7 2088.67  4646.3 2087.24  4731.7 2084.05  4764.6 2083.79
  4802.6 2082.68  4908.0 2081.87  4913.0 2080.87  4951.8 2079.66  4969.6 2077.45
  4969.9 2076.95  4974.1 2077.45  5022.0 2078.80  5039.9 2082.38  5117.3 2083.41
  5132.6 2084.78  5153.8 2088.44  5160.3 2091.28  5196.3 2098.76  5278.3 2103.47
  5313.6 2108.06  5327.2 2108.07  5349.0 2112.47  5363.8 2114.59  5408.0 2118.14
#Mann=4,-1,0
  4474.4     0.1       0  4764.6    0.07       0  4969.6    0.05       0
  4974.1    0.07       0
Bank Sta=4969.6,4974.1
Exp/Cntr=0.3,0.1

Type RM Length L Ch R = 1,19982,456,456,456
BEGIN DESCRIPTION:
Stream0165 42.0
END DESCRIPTION:
XS GIS Cut Line= 3
      1810974.97     13919775.02      1811375.00     13919525.00
      1811674.96     13919375.02
#Sta/Elev= 30
  4527.9 2140.20  4530.9 2140.20  4535.6 2138.47  4556.8 2136.05  4578.1 2130.42
  4586.9 2126.95  4593.4 2122.84  4614.6 2116.59  4629.9 2108.35  4645.3 2103.03
  4651.2 2101.84  4657.6 2098.00  4672.4 2093.59  4687.7 2087.37  4724.3 2080.42
  4793.1 2077.87  4939.9 2078.09  4949.5 2076.96  4955.4 2077.14  4964.3 2075.63
  4970.7 2072.95  4983.7 2070.91  4984.1 2070.41  4988.4 2070.91  4996.7 2072.43
  5030.4 2073.27  5156.2 2081.71  5301.9 2085.42  5321.1 2086.27  5335.0 2085.66
#Mann=6,-1,0
  4527.9     0.1       0  4793.1    0.07       0  4939.9     0.1       0
  4983.7    0.05       0  4988.4     0.1       0  5301.9    0.07       0
Bank Sta=4983.7,4988.4
Exp/Cntr=0.3,0.1

Type RM Length L Ch R = 1,19526,427,427,427
BEGIN DESCRIPTION:
Stream0165 41.0
END DESCRIPTION:
XS GIS Cut Line= 3
      1811124.99     13920325.01      1811525.00     13919925.00
      1811724.99     13919575.02
#Sta/Elev= 30
  4438.5 2121.51  4466.8 2117.96  4473.9 2115.50  4495.1 2112.12  4551.7 2105.08
  4565.8 2102.25  4579.9 2101.73  4622.4 2089.25  4636.5 2087.35  4664.8 2084.42
  4735.5 2080.24  4806.2 2074.36  4820.4 2073.68  4848.6 2074.62  4900.5 2069.14
  4902.8 2068.87  4903.2 2068.37  4907.6 2068.87  4933.5 2070.15  4990.1 2069.91
  5000.7 2071.95  5017.9 2073.30  5061.8 2074.82  5071.2 2074.35  5114.3 2077.34
  5135.9 2076.95  5216.6 2080.26  5348.0 2083.36  5367.6 2083.40  5407.3 2084.81
#Mann=6,-1,0
  4438.5    0.07       0  4900.5     0.1       0  4902.8    0.05       0
  4907.6     0.1       0  5348.0    0.07       0  5367.6     0.1       0
Bank Sta=4902.8,4907.6
Exp/Cntr=0.3,0.1

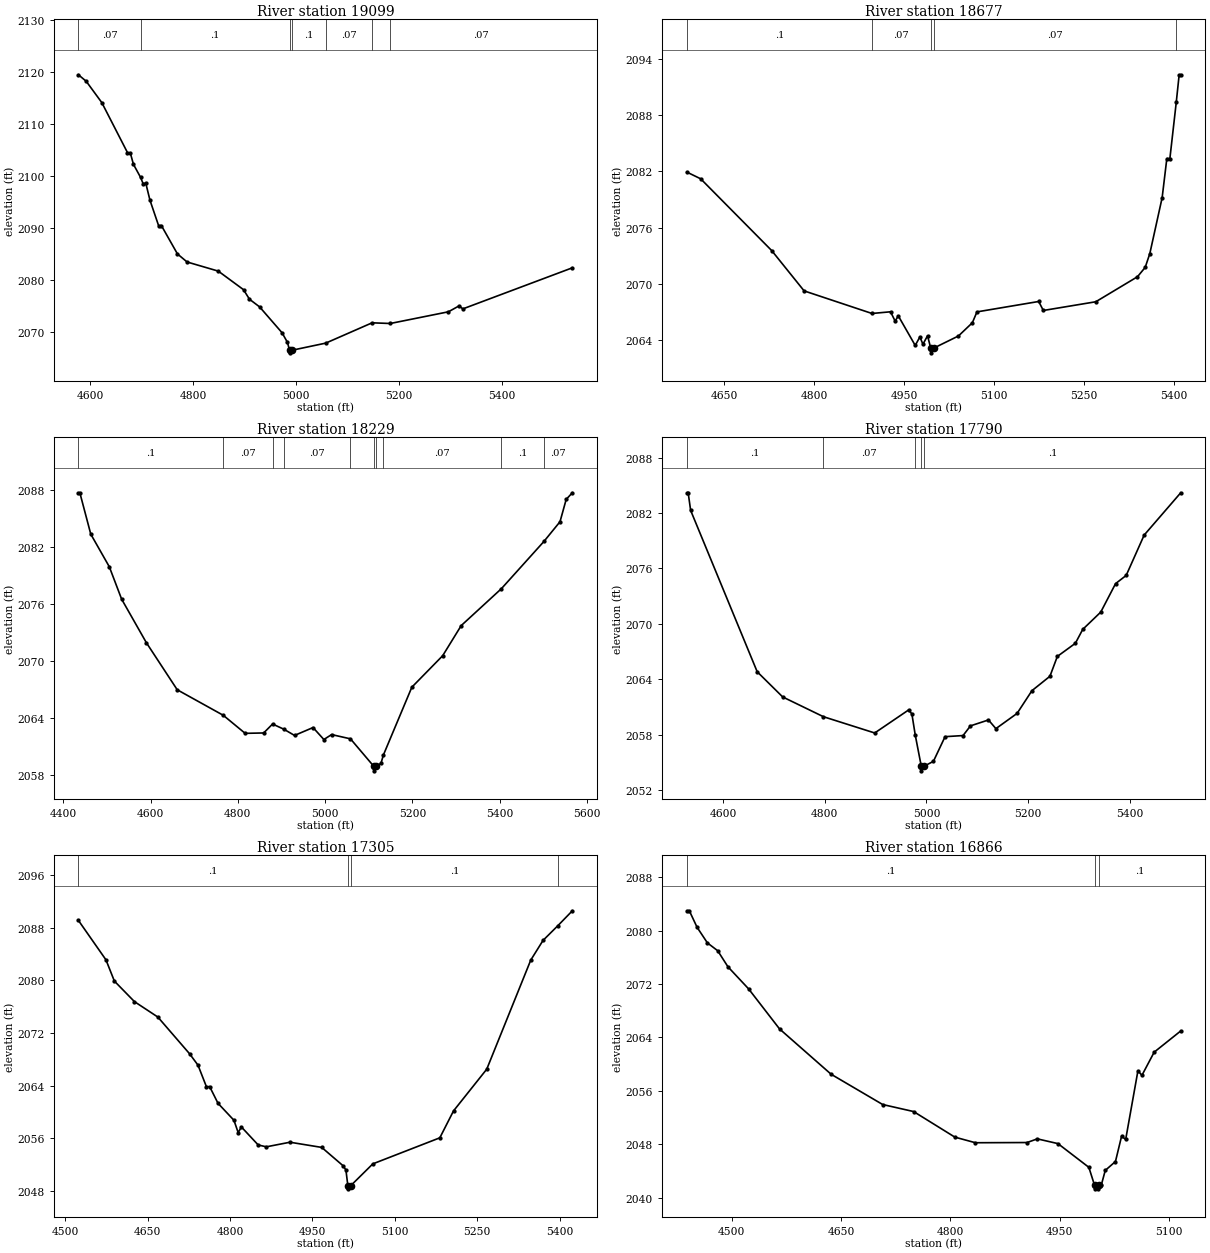
Type RM Length L Ch R = 1,19099,422,422,422
BEGIN DESCRIPTION:
Stream0165 40.0
END DESCRIPTION:
XS GIS Cut Line= 3
      1811175.00     13920425.00      1811575.00     13920275.00
      1811974.99     13919925.01
#Sta/Elev= 30
  4577.4 2119.53  4592.5 2118.28  4622.8 2114.17  4672.6 2104.55  4678.0 2104.51
  4684.2 2102.29  4697.9 2099.80  4702.9 2098.59  4708.2 2098.64  4716.2 2095.40
  4733.2 2090.43  4738.5 2090.49  4769.6 2085.04  4788.3 2083.49  4848.9 2081.73
  4897.8 2078.16  4909.4 2076.32  4929.0 2074.85  4972.6 2069.87  4983.2 2068.00
  4987.1 2066.50  4987.4 2066.00  4991.9 2066.50  5057.4 2067.87  5147.4 2071.78
  5182.7 2071.65  5295.5 2073.90  5316.4 2075.05  5323.5 2074.46  5536.1 2082.37
#Mann=7,-1,0
  4577.4    0.07       0  4697.9     0.1       0  4987.1    0.05       0
  4991.9     0.1       0  5057.4    0.07       0  5147.4     0.1       0
  5182.7    0.07       0
Bank Sta=4987.1,4991.9
Exp/Cntr=0.3,0.1

Type RM Length L Ch R = 1,18677,448,448,448
BEGIN DESCRIPTION:
Stream0165 39.0
END DESCRIPTION:
XS GIS Cut Line= 3
      1811374.96     13920524.99      1811775.00     13920625.00
      1812175.03     13920524.99
#Sta/Elev= 30
  4587.2 2081.92  4610.4 2081.20  4729.0 2073.54  4783.1 2069.24  4896.4 2066.83
  4927.4 2067.01  4935.1 2066.01  4940.3 2066.58  4968.6 2063.42  4976.4 2064.33
  4981.5 2063.55  4989.2 2064.45  4994.5 2063.13  4994.9 2062.63  4999.4 2063.13
  5040.8 2064.43  5064.0 2065.84  5071.7 2067.00  5174.8 2068.11  5182.5 2067.15
  5270.1 2068.08  5339.7 2070.75  5352.6 2071.75  5360.3 2073.22  5380.9 2079.19
  5388.7 2083.35  5393.8 2083.36  5404.5 2089.39  5409.3 2092.30  5411.9 2092.30
#Mann=5,-1,0
  4587.2     0.1       0  4896.4    0.07       0  4994.5    0.05       0
  4999.4    0.07       0  5404.5     0.1       0
Bank Sta=4994.5,4999.4
Exp/Cntr=0.3,0.1

Type RM Length L Ch R = 1,18229,439,439,439
BEGIN DESCRIPTION:
Stream0165 38.0
END DESCRIPTION:
XS GIS Cut Line= 3
      1811274.98     13920624.98      1811675.00     13921025.00
      1812075.00     13921425.00
#Sta/Elev= 30
  4434.9 2087.67  4438.5 2087.67  4463.2 2083.37  4505.6 2079.94  4533.9 2076.52
  4590.5 2071.94  4661.2 2066.98  4766.7 2064.29  4816.8 2062.39  4859.2 2062.43
  4879.6 2063.37  4905.2 2062.83  4929.9 2062.17  4972.3 2063.00  4997.1 2061.74
  5014.8 2062.26  5058.1 2061.81  5111.0 2058.94  5111.5 2058.44  5116.4 2058.94
  5127.9 2059.22  5133.3 2060.09  5198.6 2067.25  5269.3 2070.57  5311.7 2073.74
  5403.8 2077.63  5501.3 2082.61  5538.0 2084.68  5552.2 2087.04  5566.3 2087.73
#Mann=10,-1,0
  4434.9     0.1       0  4766.7    0.07       0  4879.6     0.1       0
  4905.2    0.07       0  5058.1     0.1       0  5111.0    0.05       0
  5116.4     0.1       0  5133.3    0.07       0  5403.8     0.1       0
  5501.3    0.07       0
Bank Sta=5111,5116.4
Exp/Cntr=0.3,0.1

Type RM Length L Ch R = 1,17790,485,485,485
BEGIN DESCRIPTION:
Stream0165 37.0
END DESCRIPTION:
XS GIS Cut Line= 3
      1811075.02     13921075.01      1811475.00     13921325.00
      1811875.02     13921625.02
#Sta/Elev= 30
  4528.6 2084.12  4531.5 2084.12  4536.2 2082.28  4667.1 2064.81  4717.3 2062.08
  4797.5 2059.94  4898.3 2058.18  4964.9 2060.67  4971.4 2060.25  4978.1 2057.94
  4989.9 2054.58  4990.3 2054.08  4995.3 2054.58  5013.8 2055.11  5036.7 2057.78
  5072.1 2057.90  5086.7 2058.95  5122.1 2059.59  5136.7 2058.65  5178.4 2060.30
  5207.6 2062.76  5243.0 2064.32  5257.6 2066.47  5293.0 2067.89  5307.6 2069.40
  5343.0 2071.27  5372.1 2074.35  5393.0 2075.24  5428.4 2079.61  5500.3 2084.19
#Mann=5,-1,0
  4528.6     0.1       0  4797.5    0.07       0  4978.1     0.1       0
  4989.9    0.05       0  4995.3     0.1       0
Bank Sta=4989.9,4995.3
Exp/Cntr=0.3,0.1

Type RM Length L Ch R = 1,17305,439,439,439
BEGIN DESCRIPTION:
Stream0165 36.0
END DESCRIPTION:
XS GIS Cut Line= 3
      1810975.00     13921525.00      1811375.00     13921775.00
      1811775.00     13921925.00
#Sta/Elev= 30
  4524.2 2089.12  4574.3 2083.13  4589.6 2079.90  4626.2 2076.77  4668.7 2074.43
  4726.4 2068.85  4741.8 2067.11  4757.1 2063.84  4763.0 2063.85  4778.3 2061.30
  4807.2 2058.73  4814.9 2056.86  4820.8 2057.71  4851.4 2054.97  4866.2 2054.69
  4909.2 2055.39  4967.0 2054.60  5005.7 2051.82  5011.0 2051.17  5014.5 2048.80
  5015.0 2048.30  5020.0 2048.80  5060.0 2052.10  5181.9 2056.06  5206.8 2060.15
  5267.3 2066.50  5347.4 2083.09  5369.7 2086.08  5396.7 2088.32  5423.1 2090.59
#Mann=4,-1,0
  4524.2     0.1       0  5014.5    0.05       0  5020.0     0.1       0
  5396.7    0.07       0
Bank Sta=5014.5,5020
Exp/Cntr=0.3,0.1

Type RM Length L Ch R = 1,16866,428,428,428
BEGIN DESCRIPTION:
Stream0165 35.0
END DESCRIPTION:
XS GIS Cut Line= 3
      1810875.02     13921775.02      1811275.00     13922175.00
      1811325.02     13922275.04
#Sta/Elev= 30
  4438.6 2082.96  4442.1 2082.96  4452.7 2080.49  4466.9 2078.15  4481.0 2076.98
  4495.1 2074.57  4523.4 2071.27  4565.8 2065.28  4636.6 2058.49  4707.3 2053.96
  4749.7 2052.91  4806.3 2049.08  4834.5 2048.24  4905.3 2048.27  4919.4 2048.82
  4947.7 2048.11  4990.1 2044.56  4998.0 2041.84  4998.4 2041.34  5003.0 2041.34
  5003.5 2041.84  5007.0 2041.84  5012.6 2044.10  5026.6 2045.43  5035.0 2049.23
  5040.6 2048.73  5057.4 2059.01  5062.9 2058.33  5079.7 2061.80  5116.1 2064.97
#Mann=3,-1,0
  4438.6     0.1       0  4998.0    0.05       0  5003.5     0.1       0
Bank Sta=4998,5003.5
Exp/Cntr=0.3,0.1

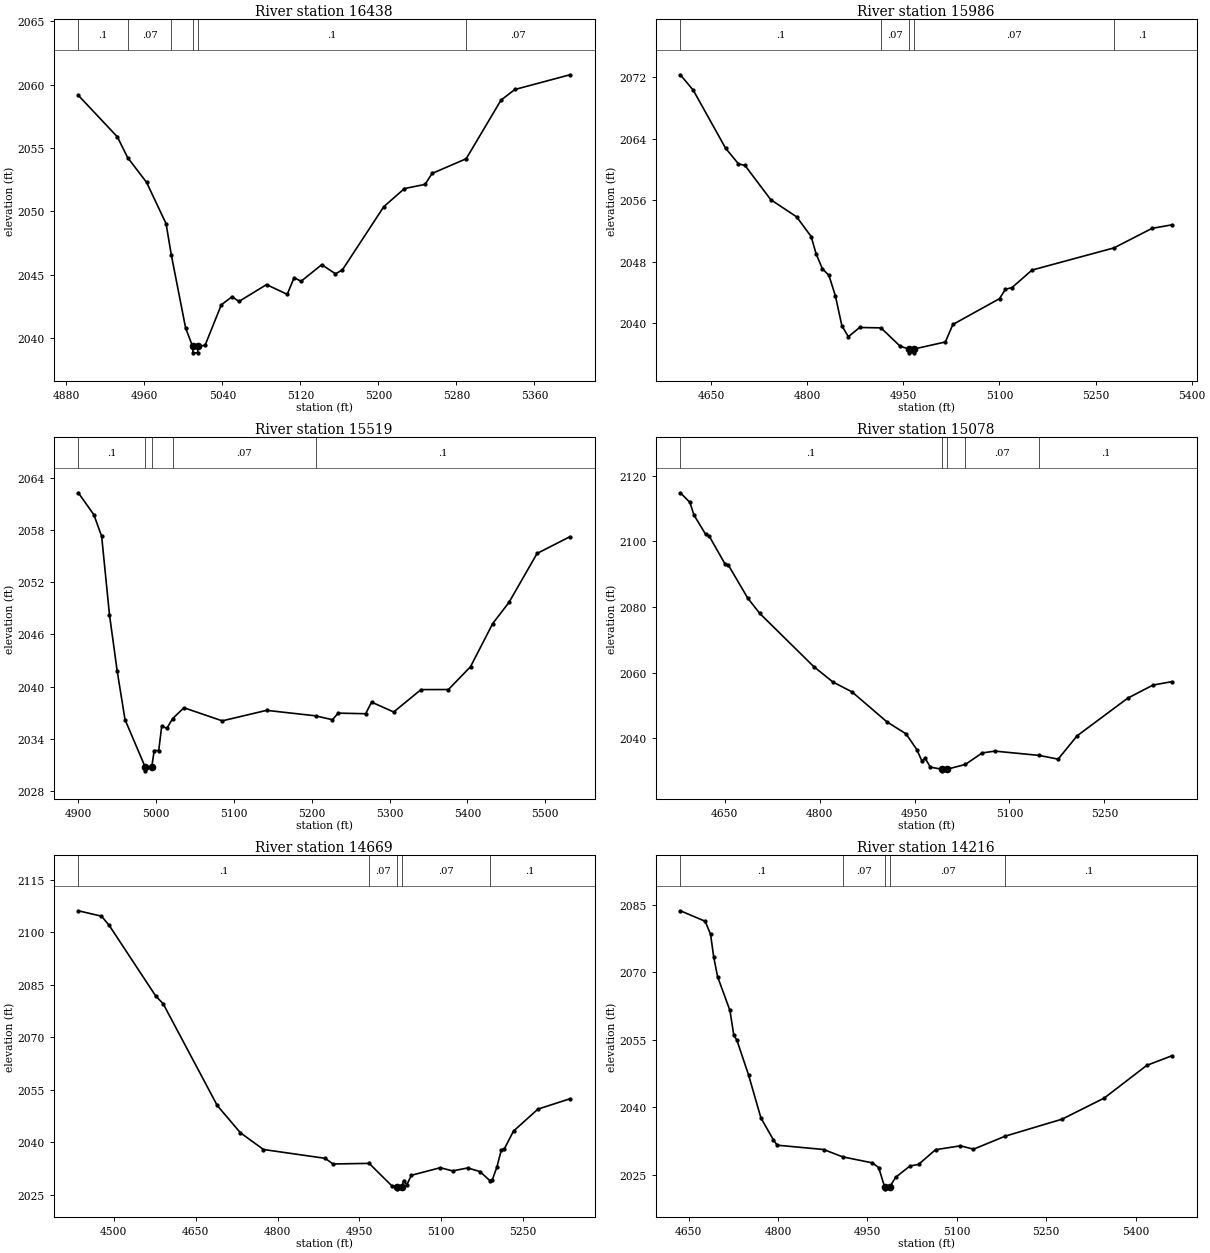
Type RM Length L Ch R = 1,16438,452,452,452
BEGIN DESCRIPTION:
Stream0165 34.0
END DESCRIPTION:
XS GIS Cut Line= 3
      1810875.00     13921975.02      1810873.45     13922123.30
      1811124.97     13922374.97
#Sta/Elev= 30
  4892.3 2059.15  4932.3 2055.88  4942.9 2054.24  4962.3 2052.29  4982.3 2049.03
  4987.6 2046.59  5002.3 2040.82  5009.5 2039.35  5009.9 2038.85  5014.6 2038.85
  5015.1 2039.35  5022.3 2039.45  5038.9 2042.63  5050.0 2043.28  5057.0 2042.90
  5085.3 2044.23  5106.5 2043.46  5113.6 2044.78  5120.7 2044.49  5141.9 2045.80
  5156.0 2045.08  5163.1 2045.39  5205.5 2050.37  5226.7 2051.80  5247.9 2052.13
  5255.0 2052.99  5290.0 2054.15  5325.7 2058.77  5339.9 2059.61  5396.4 2060.77
#Mann=6,-1,0
  4892.3     0.1       0  4942.9    0.07       0  4987.6     0.1       0
  5009.5    0.05       0  5015.1     0.1       0  5290.0    0.07       0
Bank Sta=5009.5,5015.1
Exp/Cntr=0.3,0.1

Type RM Length L Ch R = 1,15986,467,467,467
BEGIN DESCRIPTION:
Stream0165 33.0
END DESCRIPTION:
XS GIS Cut Line= 3
      1810124.97     13922325.00      1810525.00     13922275.00
      1810874.96     13922374.99
#Sta/Elev= 30
  4602.1 2072.27  4622.3 2070.26  4672.7 2062.74  4692.8 2060.71  4702.9 2060.51
  4743.2 2056.06  4783.5 2053.84  4806.2 2051.28  4813.8 2049.07  4823.8 2047.08
  4833.9 2046.25  4844.0 2043.58  4854.1 2039.72  4864.2 2038.28  4881.8 2039.48
  4915.1 2039.43  4944.8 2037.07  4958.1 2036.69  4958.6 2036.19  4966.3 2036.19
  4966.8 2036.69  5015.6 2037.60  5027.3 2039.87  5100.1 2043.22  5109.2 2044.43
  5119.6 2044.66  5150.8 2046.93  5278.8 2049.81  5338.0 2052.34  5369.2 2052.80
#Mann=5,-1,0
  4602.1     0.1       0  4915.1    0.07       0  4958.1    0.05       0
  4966.8    0.07       0  5278.8     0.1       0
Bank Sta=4958.1,4966.8
Exp/Cntr=0.3,0.1

Type RM Length L Ch R = 1,15519,441,441,441
BEGIN DESCRIPTION:
Stream0165 32.0
END DESCRIPTION:
XS GIS Cut Line= 3
      1810225.01     13922675.00      1810325.00     13922675.00
      1810725.00     13923025.00
#Sta/Elev= 30
  4900.1 2062.33  4920.1 2059.80  4930.1 2057.31  4940.1 2048.30  4950.1 2041.75
  4960.1 2036.19  4985.7 2030.79  4986.2 2030.29  4994.5 2030.79  4997.6 2032.63
  5003.4 2032.63  5007.2 2035.42  5013.9 2035.20  5021.2 2036.30  5035.7 2037.56
  5085.0 2036.05  5142.0 2037.26  5204.8 2036.63  5226.5 2036.18  5234.0 2036.94
  5269.2 2036.87  5276.8 2038.21  5305.2 2037.07  5340.3 2039.65  5375.5 2039.66
  5403.9 2042.29  5432.4 2047.26  5453.3 2049.70  5489.4 2055.34  5531.6 2057.27
#Mann=5,-1,0
  4900.1     0.1       0  4985.7    0.05       0  4994.5     0.1       0
  5021.2    0.07       0  5204.8     0.1       0
Bank Sta=4985.7,4994.5
Exp/Cntr=0.3,0.1

Type RM Length L Ch R = 1,15078,409,409,409
BEGIN DESCRIPTION:
Stream0165 31.0
END DESCRIPTION:
XS GIS Cut Line= 3
      1809974.99     13922925.00      1810375.00     13923075.00
      1810724.99     13923075.00
#Sta/Elev= 30
  4579.7 2114.77  4594.8 2111.85  4601.1 2108.03  4619.8 2102.06  4625.1 2101.63
  4650.0 2093.18  4655.4 2092.79  4686.5 2082.59  4705.2 2078.02  4790.6 2061.80
  4820.9 2057.11  4851.2 2054.08  4906.3 2044.96  4936.6 2041.29  4953.5 2036.51
  4961.5 2033.06  4966.9 2033.81  4974.9 2031.17  4992.7 2030.54  4993.2 2030.04
  5001.5 2030.54  5030.2 2031.99  5056.9 2035.50  5076.9 2036.05  5147.1 2034.74
  5176.9 2033.60  5206.9 2040.71  5286.9 2052.18  5326.9 2056.18  5356.9 2057.22
#Mann=5,-1,0
  4579.7     0.1       0  4992.7    0.05       0  5001.5     0.1       0
  5030.2    0.07       0  5147.1     0.1       0
Bank Sta=4992.7,5001.5
Exp/Cntr=0.3,0.1

Type RM Length L Ch R = 1,14669,453,453,453
BEGIN DESCRIPTION:
Stream0165 30.0
END DESCRIPTION:
XS GIS Cut Line= 3
      1809974.97     13923825.03      1810375.00     13923425.00
      1810674.97     13923275.01
#Sta/Elev= 30
  4434.9 2106.12  4477.4 2104.58  4491.5 2101.96  4576.4 2081.87  4590.5 2079.55
  4689.5 2050.53  4731.9 2042.74  4774.3 2037.95  4887.5 2035.43  4901.6 2033.82
  4968.0 2033.99  5009.0 2027.66  5018.5 2027.22  5019.0 2026.72  5027.4 2027.22
  5031.4 2029.08  5037.0 2027.87  5045.3 2030.59  5098.4 2032.75  5120.8 2031.84
  5148.8 2032.69  5171.1 2031.64  5190.1 2028.95  5193.5 2029.22  5201.9 2032.83
  5210.3 2037.86  5215.8 2038.15  5232.6 2043.22  5277.3 2049.48  5336.0 2052.44
#Mann=5,-1,0
  4434.9     0.1       0  4968.0    0.07       0  5018.5    0.05       0
  5027.4    0.07       0  5190.1     0.1       0
Bank Sta=5018.5,5027.4
Exp/Cntr=0.3,0.1

Type RM Length L Ch R = 1,14216,448,448,448
BEGIN DESCRIPTION:
Stream0165 29.0
END DESCRIPTION:
XS GIS Cut Line= 3
      1810175.00     13923925.00      1810525.00     13923825.00
      1810875.01     13923524.99
#Sta/Elev= 30
  4636.0 2083.62  4677.6 2081.30  4686.7 2078.40  4691.9 2073.43  4698.4 2069.02
  4719.2 2061.49  4725.7 2056.01  4730.9 2054.87  4750.4 2047.20  4771.2 2037.63
  4792.0 2032.80  4798.5 2031.58  4876.5 2030.62  4908.1 2029.00  4958.4 2027.65
  4968.8 2026.61  4978.6 2022.39  4979.1 2021.89  4987.6 2022.39  4997.4 2024.47
  5021.4 2026.97  5035.7 2027.31  5064.2 2030.58  5105.9 2031.44  5127.9 2030.69
  5181.1 2033.58  5276.6 2037.36  5347.4 2042.05  5418.7 2049.30  5461.0 2051.44
#Mann=5,-1,0
  4636.0     0.1       0  4908.1    0.07       0  4978.6    0.05       0
  4987.6    0.07       0  5181.1     0.1       0
Bank Sta=4978.6,4987.6
Exp/Cntr=0.3,0.1

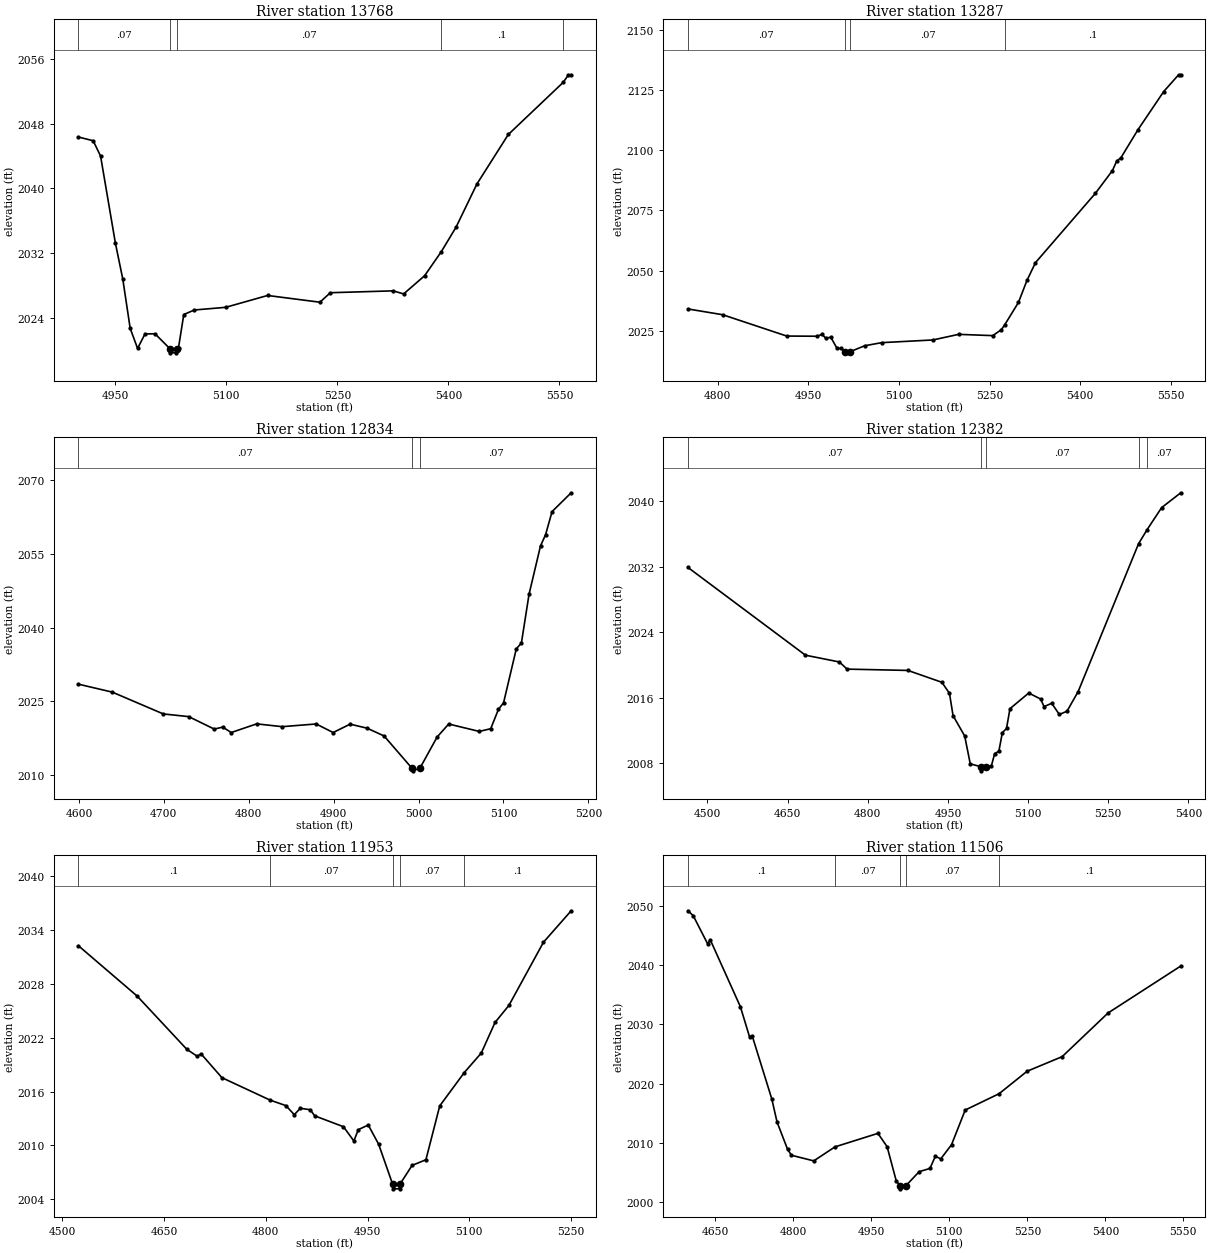
Type RM Length L Ch R = 1,13768,481,481,481
BEGIN DESCRIPTION:
Stream0165 28.0
END DESCRIPTION:
XS GIS Cut Line= 3
      1810775.00     13924224.99      1810775.00     13924125.00
      1811175.01     13923724.99
#Sta/Elev= 30
  4900.1 2046.34  4920.1 2045.88  4930.1 2043.99  4950.1 2033.27  4960.1 2028.83
  4970.1 2022.76  4980.1 2020.28  4990.1 2022.07  5003.6 2022.09  5023.9 2020.24
  5024.4 2019.74  5032.4 2019.74  5032.9 2020.24  5035.4 2020.38  5042.5 2024.46
  5056.7 2025.02  5099.1 2025.35  5155.7 2026.81  5226.4 2025.98  5240.5 2027.15
  5325.4 2027.38  5339.5 2027.00  5367.8 2029.24  5390.4 2032.21  5410.2 2035.21
  5438.5 2040.55  5480.9 2046.65  5555.0 2053.07  5562.2 2054.01  5565.8 2054.01
#Mann=5,-1,0
  4900.1    0.07       0  5023.9    0.05       0  5032.9    0.07       0
  5390.4     0.1       0  5555.0    0.07       0
Bank Sta=5023.9,5032.9
Exp/Cntr=0.3,0.1

Type RM Length L Ch R = 1,13287,453,453,453
BEGIN DESCRIPTION:
Stream0165 27.0
END DESCRIPTION:
XS GIS Cut Line= 3
      1811025.03     13924374.98      1811225.00     13924225.00
      1811625.03     13923824.97
#Sta/Elev= 30
  4750.7 2034.00  4808.0 2031.61  4914.2 2022.73  4964.2 2022.66  4972.5 2023.40
  4978.8 2021.87  4987.1 2022.24  4997.5 2017.57  5004.2 2017.57  5010.3 2016.25
  5010.8 2015.75  5019.3 2016.25  5043.1 2018.69  5071.4 2019.99  5156.2 2021.11
  5198.7 2023.44  5255.2 2022.91  5269.4 2025.37  5274.9 2027.38  5297.7 2036.72
  5311.8 2045.87  5325.9 2053.28  5424.9 2082.06  5453.2 2091.54  5460.3 2095.48
  5467.4 2096.94  5495.6 2108.59  5538.1 2124.43  5562.8 2131.42  5566.4 2131.42
#Mann=4,-1,0
  4750.7    0.07       0  5010.3    0.05       0  5019.3    0.07       0
  5274.9     0.1       0
Bank Sta=5010.3,5019.3
Exp/Cntr=0.3,0.1

Type RM Length L Ch R = 1,12834,452,452,452
BEGIN DESCRIPTION:
Stream0165 26.0
END DESCRIPTION:
XS GIS Cut Line= 3
      1811174.99     13924425.00      1811575.00     13924425.00
      1811725.01     13924325.00
#Sta/Elev= 30
  4599.4 2028.48  4639.4 2026.86  4699.4 2022.43  4729.4 2021.88  4759.4 2019.35
  4769.4 2019.75  4779.4 2018.65  4809.4 2020.41  4839.4 2019.84  4879.4 2020.39
  4899.4 2018.65  4919.4 2020.35  4939.4 2019.53  4959.4 2017.95  4992.4 2011.36
  4992.9 2010.86  5001.5 2011.36  5021.9 2017.75  5035.5 2020.38  5071.5 2018.87
  5085.0 2019.43  5094.1 2023.37  5100.1 2024.69  5115.1 2035.67  5121.1 2036.83
  5130.1 2046.76  5143.6 2056.59  5149.6 2058.88  5157.2 2063.56  5179.7 2067.39
#Mann=3,-1,0
  4599.4    0.07       0  4992.4    0.05       0  5001.5    0.07       0
Bank Sta=4992.4,5001.5
Exp/Cntr=0.3,0.1

Type RM Length L Ch R = 1,12382,429,429,429
BEGIN DESCRIPTION:
Stream0165 25.0
END DESCRIPTION:
XS GIS Cut Line= 3
      1811074.97     13924424.96      1811425.00     13924825.00
      1811675.02     13925125.02
#Sta/Elev= 30
  4463.7 2031.91  4683.5 2021.20  4747.1 2020.37  4761.3 2019.50  4875.2 2019.34
  4938.8 2017.89  4953.0 2016.54  4959.7 2013.82  4981.5 2011.33  4991.9 2007.93
  5012.2 2007.58  5012.7 2007.08  5021.3 2007.58  5031.1 2007.62  5037.6 2009.19
  5045.4 2009.47  5051.9 2011.74  5059.7 2012.25  5066.2 2014.67  5101.3 2016.58
  5123.5 2015.85  5130.0 2014.92  5144.3 2015.33  5158.6 2013.96  5172.9 2014.36
  5193.8 2016.76  5306.8 2034.81  5322.9 2036.54  5350.0 2039.22  5385.8 2041.03
#Mann=5,-1,0
  4463.7    0.07       0  5012.2    0.05       0  5021.3    0.07       0
  5306.8   0.035       0  5322.9    0.07       0
Bank Sta=5012.2,5021.3
Exp/Cntr=0.3,0.1

Type RM Length L Ch R = 1,11953,447,447,447
BEGIN DESCRIPTION:
Stream0165 24.0
END DESCRIPTION:
XS GIS Cut Line= 3
      1810924.99     13924974.99      1811325.00     13925225.00
      1811575.03     13925275.01
#Sta/Elev= 30
  4523.6 2032.24  4610.3 2026.63  4683.4 2020.71  4698.7 2019.93  4704.6 2020.19
  4735.3 2017.54  4806.4 2015.04  4829.6 2014.43  4842.0 2013.42  4850.9 2014.13
  4865.6 2013.97  4872.1 2013.29  4914.5 2012.08  4929.9 2010.49  4936.4 2011.75
  4951.1 2012.27  4966.4 2010.13  4987.1 2005.66  4987.6 2005.16  4997.2 2005.16
  4997.7 2005.66  5015.7 2007.77  5036.1 2008.40  5056.5 2014.40  5092.7 2018.11
  5117.7 2020.28  5138.1 2023.70  5158.5 2025.59  5209.5 2032.63  5250.3 2036.13
#Mann=5,-1,0
  4523.6     0.1       0  4806.4    0.07       0  4987.1    0.05       0
  4997.7    0.07       0  5092.7     0.1       0
Bank Sta=4987.1,4997.7
Exp/Cntr=0.3,0.1

Type RM Length L Ch R = 1,11506,455,455,455
BEGIN DESCRIPTION:
Stream0165 23.0
END DESCRIPTION:
XS GIS Cut Line= 3
      1810775.01     13925575.00      1811175.00     13925625.00
      1811699.69     13925478.73
#Sta/Elev= 30
  4597.3 2049.15  4607.4 2048.32  4635.1 2043.58  4640.1 2044.27  4698.1 2032.98
  4715.7 2027.90  4720.7 2028.10  4758.5 2017.44  4768.6 2013.55  4788.8 2008.96
  4796.3 2007.95  4839.2 2007.00  4880.0 2009.36  4962.6 2011.64  4980.3 2009.39
  4997.9 2003.62  5005.4 2002.79  5005.9 2002.29  5016.1 2002.79  5041.9 2005.18
  5062.7 2005.73  5073.1 2007.78  5083.5 2007.34  5104.2 2009.73  5130.5 2015.57
  5195.6 2018.32  5249.6 2022.11  5317.0 2024.57  5405.3 2031.93  5545.1 2039.84
#Mann=5,-1,0
  4597.3     0.1       0  4880.0    0.07       0  5005.4    0.05       0
  5016.1    0.07       0  5195.6     0.1       0
Bank Sta=5005.4,5016.1
Exp/Cntr=0.3,0.1

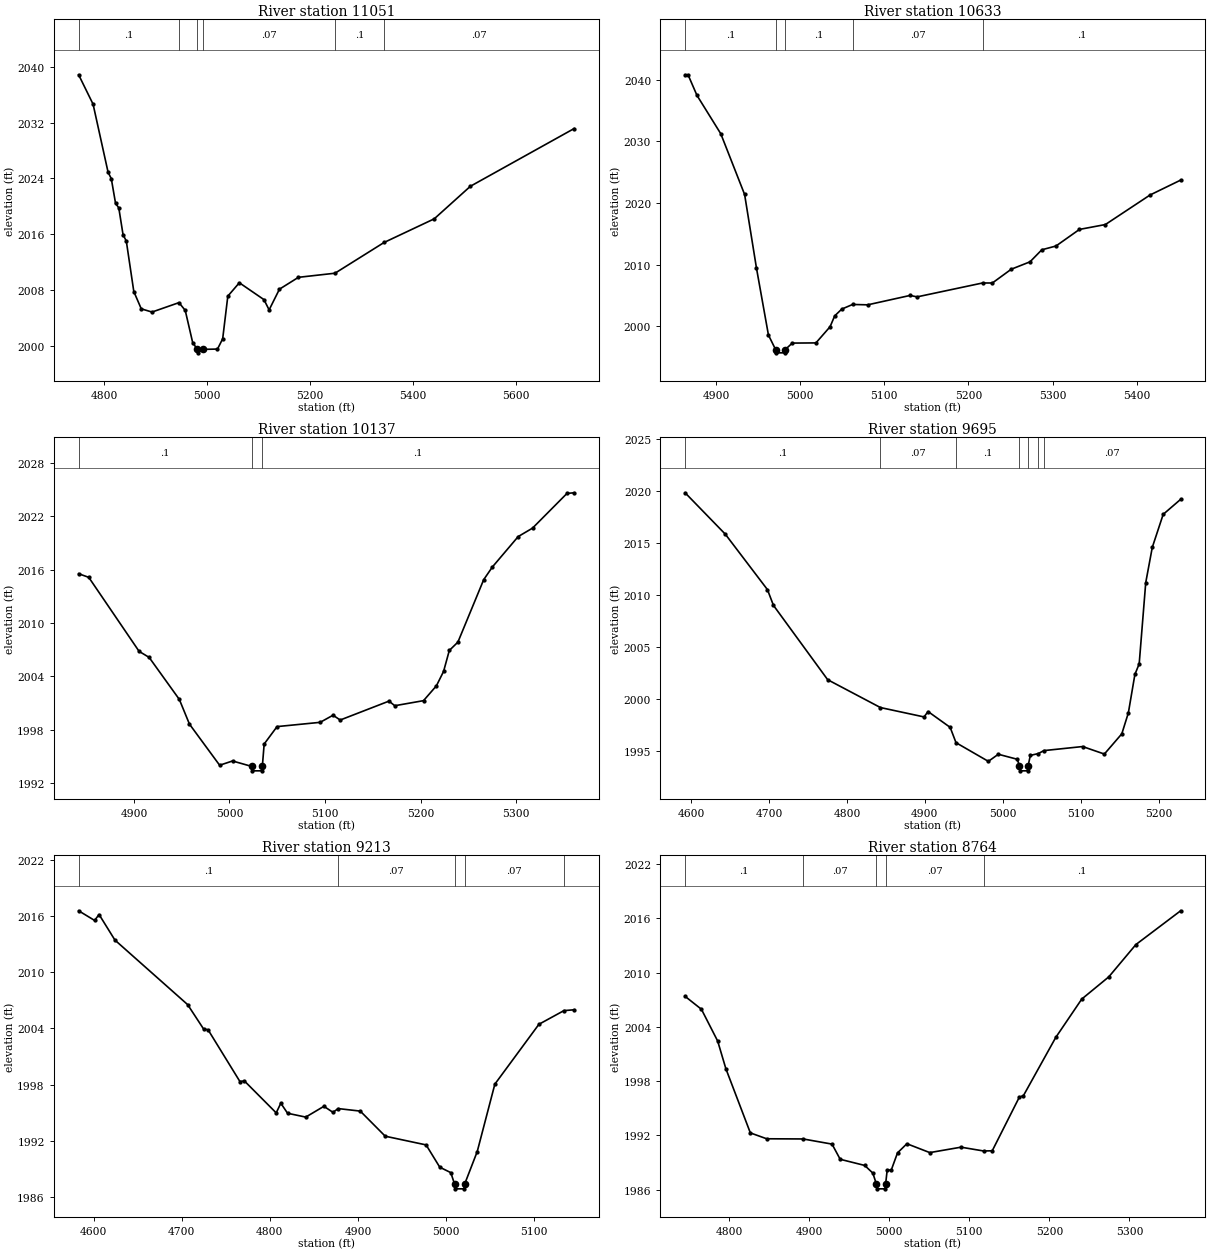
Type RM Length L Ch R = 1,11051,418,418,418
BEGIN DESCRIPTION:
Stream0165 22.0
END DESCRIPTION:
XS GIS Cut Line= 3
      1810825.03     13925875.02      1811025.00     13926025.00
      1811736.13     13925965.29
#Sta/Elev= 30
  4750.3 2038.87  4778.4 2034.65  4807.6 2024.88  4813.8 2023.98  4822.1 2020.43
  4828.4 2019.78  4836.7 2015.92  4843.0 2015.03  4857.6 2007.78  4872.1 2005.30
  4893.0 2004.84  4945.4 2006.19  4957.6 2005.08  4972.1 2000.45  4981.2 1999.49
  4981.7 1998.99  4992.3 1999.49  5020.3 1999.53  5030.4 2001.00  5040.4 2007.12
  5062.8 2009.04  5110.7 2006.62  5120.7 2005.15  5140.8 2008.12  5177.7 2009.82
  5248.8 2010.41  5344.3 2014.82  5441.8 2018.21  5512.1 2022.88  5713.9 2031.16
#Mann=6,-1,0
  4750.3     0.1       0  4945.4    0.07       0  4981.2    0.05       0
  4992.3    0.07       0  5248.8     0.1       0  5344.3    0.07       0
Bank Sta=4981.2,4992.3
Exp/Cntr=0.3,0.1

Type RM Length L Ch R = 1,10633,496,496,496
BEGIN DESCRIPTION:
Stream0165 21.0
END DESCRIPTION:
XS GIS Cut Line= 3
      1811075.01     13926424.99      1811175.00     13926325.00
      1811574.98     13926125.01
#Sta/Elev= 30
  4863.4 2040.78  4866.9 2040.78  4877.5 2037.44  4905.8 2031.22  4934.1 2021.38
  4948.2 2009.43  4962.4 1998.60  4971.0 1996.22  4971.5 1995.72  4981.6 1995.72
  4982.1 1996.22  4990.7 1997.30  5018.8 1997.33  5035.6 1999.95  5041.1 2001.71
  5049.5 2002.81  5062.4 2003.56  5080.3 2003.50  5130.6 2005.02  5139.0 2004.79
  5216.7 2007.04  5228.4 2007.04  5250.8 2009.27  5273.1 2010.47  5287.1 2012.42
  5303.9 2013.03  5331.8 2015.72  5362.6 2016.51  5415.7 2021.30  5452.0 2023.71
#Mann=5,-1,0
  4863.4     0.1       0  4971.0    0.05       0  4982.1     0.1       0
  5062.4    0.07       0  5216.7     0.1       0
Bank Sta=4971,4982.1
Exp/Cntr=0.3,0.1

Type RM Length L Ch R = 1,10137,442,442,442
BEGIN DESCRIPTION:
Stream0165 20.0
END DESCRIPTION:
XS GIS Cut Line= 3
      1811374.98     13926725.01      1811525.00     13926675.00
      1811825.01     13926475.00
#Sta/Elev= 30
  4842.1 2015.54  4852.7 2015.13  4905.4 2006.80  4915.9 2006.12  4947.5 2001.39
  4958.1 1998.61  4989.7 1993.98  5003.2 1994.46  5023.2 1993.85  5023.7 1993.35
  5033.9 1993.35  5034.4 1993.85  5036.3 1996.37  5049.8 1998.33  5094.9 1998.81
  5108.4 1999.61  5115.9 1999.07  5167.0 2001.20  5173.0 2000.68  5203.1 2001.25
  5216.6 2002.92  5224.1 2004.54  5230.1 2006.90  5239.1 2007.84  5266.1 2014.87
  5275.2 2016.30  5302.2 2019.72  5317.2 2020.67  5353.3 2024.58  5360.8 2024.65
#Mann=3,-1,0
  4842.1     0.1       0  5023.2    0.05       0  5034.4     0.1       0
Bank Sta=5023.2,5034.4
Exp/Cntr=0.3,0.1

Type RM Length L Ch R = 1,9695,482,482,482
BEGIN DESCRIPTION:
Stream0165 19.0
END DESCRIPTION:
XS GIS Cut Line= 3
      1811424.96     13927075.01      1811825.00     13926975.00
      1812025.04     13926874.98
#Sta/Elev= 30
  4592.3 2019.81  4643.9 2015.84  4698.0 2010.52  4705.7 2009.01  4775.3 2001.88
  4843.0 1999.21  4899.0 1998.31  4904.1 1998.83  4932.5 1997.31  4940.0 1995.84
  4981.5 1994.05  4994.3 1994.73  5018.6 1994.25  5021.4 1993.64  5021.9 1993.14
  5032.1 1993.14  5032.6 1993.64  5035.4 1994.62  5045.8 1994.80  5052.7 1995.08
  5102.5 1995.47  5130.4 1994.75  5152.8 1996.69  5161.2 1998.70  5169.6 2002.39
  5175.1 2003.40  5183.5 2011.19  5191.9 2014.57  5205.9 2017.74  5228.3 2019.18
#Mann=7,-1,0
  4592.3     0.1       0  4843.0    0.07       0  4940.0     0.1       0
  5021.4    0.05       0  5032.6     0.1       0  5045.8   0.035       0
  5052.7    0.07       0
Bank Sta=5021.4,5032.6
Exp/Cntr=0.3,0.1

Type RM Length L Ch R = 1,9213,449,449,449
BEGIN DESCRIPTION:
Stream0165 18.0
END DESCRIPTION:
XS GIS Cut Line= 3
      1811574.98     13927475.00      1811975.00     13927375.00
      1812124.97     13927375.00
#Sta/Elev= 30
  4583.1 2016.55  4601.2 2015.52  4606.3 2016.15  4624.3 2013.42  4706.8 2006.53
  4724.8 2003.94  4730.0 2003.84  4766.1 1998.32  4771.2 1998.38  4807.3 1994.97
  4812.5 1996.00  4820.2 1994.93  4840.8 1994.52  4861.4 1995.67  4871.7 1995.03
  4877.6 1995.43  4902.7 1995.16  4931.0 1992.48  4977.4 1991.55  4992.9 1989.17
  5005.4 1988.59  5009.7 1987.36  5010.2 1986.86  5020.6 1986.86  5021.1 1987.36
  5035.4 1990.84  5055.4 1998.04  5105.4 2004.43  5133.8 2005.89  5145.4 2005.98
#Mann=5,-1,0
  4583.1     0.1       0  4877.6    0.07       0  5009.7    0.05       0
  5021.1    0.07       0  5133.8     0.1       0
Bank Sta=5009.7,5021.1
Exp/Cntr=0.3,0.1

Type RM Length L Ch R = 1,8764,467,467,467
BEGIN DESCRIPTION:
Stream0165 17.0
END DESCRIPTION:
XS GIS Cut Line= 3
      1811775.04     13927824.99      1812025.00     13927775.00
      1812374.99     13927675.00
#Sta/Elev= 30
  4745.0 2007.38  4765.4 2005.95  4785.7 2002.43  4795.9 1999.38  4826.5 1992.27
  4846.9 1991.62  4892.4 1991.60  4928.5 1991.03  4938.7 1989.35  4969.3 1988.67
  4979.5 1987.82  4984.0 1986.58  4984.5 1986.08  4994.9 1986.08  4995.4 1986.58
  4997.4 1988.16  5002.5 1988.16  5010.3 1990.06  5022.0 1991.07  5050.6 1990.09
  5089.6 1990.69  5117.8 1990.27  5128.6 1990.29  5162.4 1996.22  5167.6 1996.40
  5207.9 2002.83  5240.4 2007.08  5274.2 2009.54  5308.0 2013.11  5363.9 2016.85
#Mann=5,-1,0
  4745.0     0.1       0  4892.4    0.07       0  4984.0    0.05       0
  4995.4    0.07       0  5117.8     0.1       0
Bank Sta=4984,4995.4
Exp/Cntr=0.3,0.1