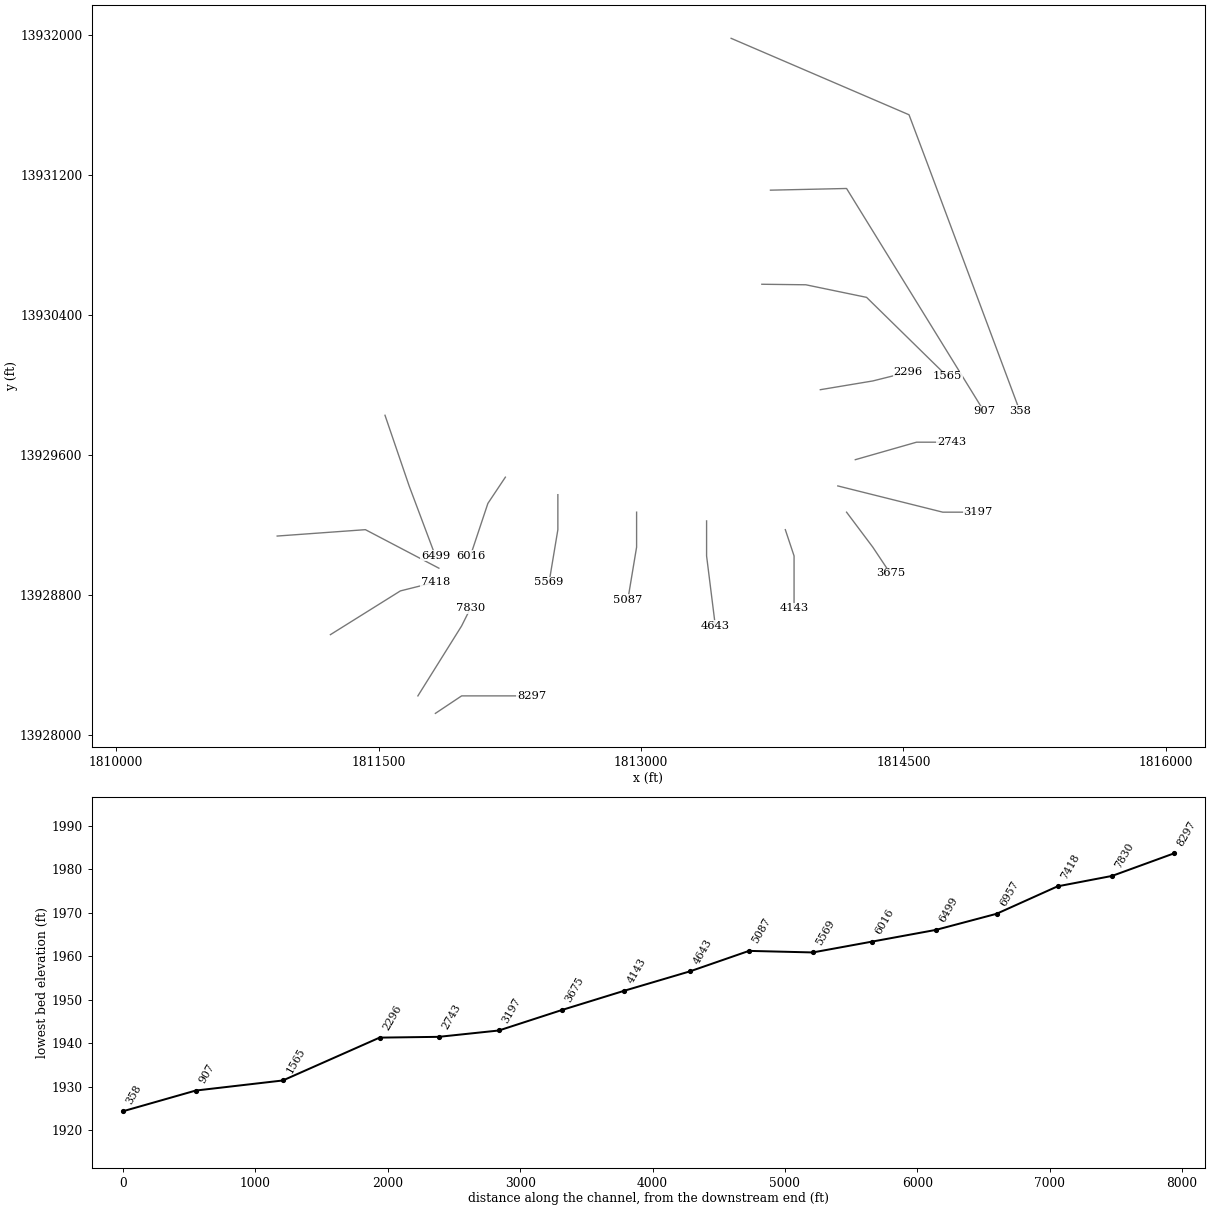
HEC-RAS study Stream0165.prj: Stream0165 Base Level Engineering

--- Stream0165.g01 (geometry) --- (continued)

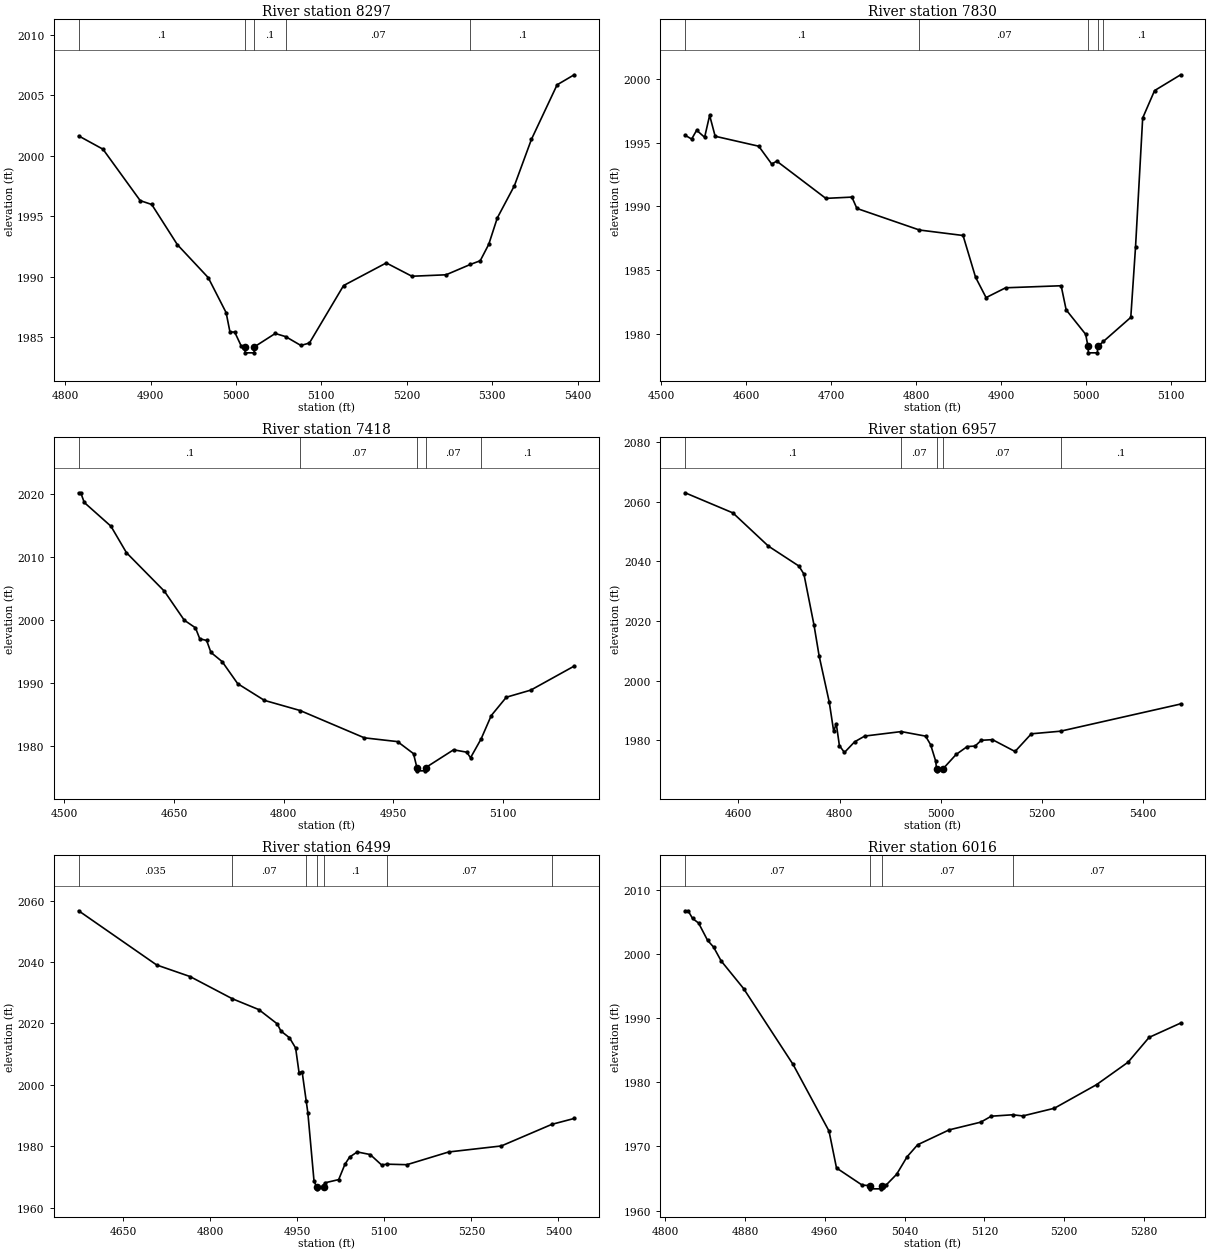
Type RM Length L Ch R = 1,8297,467,467,467
BEGIN DESCRIPTION:
Stream0165 16.0
END DESCRIPTION:
XS GIS Cut Line= 3
      1811825.04     13928125.03      1811975.00     13928225.00
      1812374.97     13928225.00
#Sta/Elev= 30
  4815.8 2001.63  4844.3 2000.53  4887.9 1996.28  4901.4 1995.96  4931.4 1992.64
  4967.5 1989.92  4988.5 1987.02  4993.0 1985.42  4998.5 1985.42  5006.0 1984.29
  5010.3 1984.20  5010.8 1983.70  5021.2 1983.70  5021.7 1984.20  5046.0 1985.30
  5058.2 1985.04  5076.0 1984.31  5086.0 1984.51  5126.0 1989.26  5176.0 1991.13
  5206.0 1990.03  5246.0 1990.15  5274.6 1991.01  5286.0 1991.31  5296.0 1992.67
  5306.0 1994.85  5326.0 1997.51  5346.0 2001.35  5376.0 2005.85  5396.0 2006.68
#Mann=5,-1,0
  4815.8     0.1       0  5010.3    0.05       0  5021.7     0.1       0
  5058.2    0.07       0  5274.6     0.1       0
Bank Sta=5010.3,5021.7
Exp/Cntr=0.3,0.1

Type RM Length L Ch R = 1,7830,412,412,412
BEGIN DESCRIPTION:
Stream0165 15.0
END DESCRIPTION:
XS GIS Cut Line= 3
      1811724.99     13928224.98      1811975.00     13928625.00
      1812024.99     13928724.98
#Sta/Elev= 30
  4528.0 1995.58  4535.7 1995.28  4541.6 1995.97  4551.0 1995.42  4556.9 1997.14
  4563.4 1995.50  4614.7 1994.72  4630.0 1993.32  4635.9 1993.55  4693.7 1990.63
  4724.4 1990.73  4730.3 1989.84  4803.9 1988.15  4855.3 1987.72  4870.0 1984.45
  4882.4 1982.85  4905.4 1983.62  4970.8 1983.78  4976.7 1981.89  4999.7 1979.97
  5002.4 1979.02  5002.9 1978.52  5013.4 1978.52  5013.9 1979.02  5020.5 1979.41
  5052.8 1981.30  5058.4 1986.83  5066.8 1996.93  5080.8 1999.08  5111.5 2000.32
#Mann=5,-1,0
  4528.0     0.1       0  4803.9    0.07       0  5002.4    0.05       0
  5013.9    0.07       0  5020.5     0.1       0
Bank Sta=5002.4,5013.9
Exp/Cntr=0.3,0.1

Type RM Length L Ch R = 1,7418,461,461,461
BEGIN DESCRIPTION:
Stream0165 14.0
END DESCRIPTION:
XS GIS Cut Line= 3
      1811225.00     13928575.00      1811625.00     13928825.00
      1811825.05     13928875.01
#Sta/Elev= 30
  4519.5 2020.27  4522.4 2020.27  4527.2 2018.73  4563.7 2014.96  4584.9 2010.76
  4636.8 2004.64  4664.0 2000.04  4679.3 1998.83  4685.2 1997.09  4694.6 1996.82
  4700.5 1994.92  4715.8 1993.47  4737.1 1989.96  4773.6 1987.31  4822.4 1985.70
  4910.4 1981.36  4955.8 1980.76  4977.6 1978.85  4982.3 1976.62  4982.8 1976.12
  4993.6 1976.12  4994.1 1976.62  5032.4 1979.46  5050.5 1979.08  5055.6 1978.19
  5070.1 1981.19  5084.0 1984.90  5104.6 1987.81  5138.1 1988.94  5197.4 1992.75
#Mann=5,-1,0
  4519.5     0.1       0  4822.4    0.07       0  4982.3    0.05       0
  4994.1    0.07       0  5070.1     0.1       0
Bank Sta=4982.3,4994.1
Exp/Cntr=0.3,0.1

Type RM Length L Ch R = 1,6957,458,458,458
BEGIN DESCRIPTION:
Stream0165 13.0
END DESCRIPTION:
XS GIS Cut Line= 3
      1810920.73     13929138.53      1811425.00     13929175.00
      1811845.00     13928954.82
#Sta/Elev= 30
  4494.5 2062.95  4589.0 2056.21  4659.2 2045.08  4719.4 2038.42  4729.4 2035.73
  4749.4 2018.62  4759.5 2008.31  4779.5 1992.85  4788.3 1983.04  4793.4 1985.60
  4799.6 1978.24  4809.6 1975.95  4829.6 1979.51  4849.7 1981.45  4921.8 1982.95
  4970.0 1981.43  4980.0 1978.54  4990.1 1973.00  4991.7 1970.30  4992.2 1969.80
  5003.5 1970.30  5030.4 1975.29  5052.4 1977.94  5067.8 1978.09  5080.1 1980.03
  5102.2 1980.25  5146.9 1976.28  5179.1 1982.21  5236.8 1983.08  5474.3 1992.18
#Mann=5,-1,0
  4494.5     0.1       0  4921.8    0.07       0  4991.7    0.05       0
  5003.5    0.07       0  5236.8     0.1       0
Bank Sta=4991.7,5003.5
Exp/Cntr=0.3,0.1

Type RM Length L Ch R = 1,6499,483,483,483
BEGIN DESCRIPTION:
Stream0165 12.0
END DESCRIPTION:
XS GIS Cut Line= 3
      1811537.00     13929828.81      1811675.00     13929425.00
      1811824.99     13929025.04
#Sta/Elev= 30
  4573.3 2056.74  4707.8 2039.07  4765.2 2035.31  4838.0 2028.08  4883.8 2024.53
  4915.5 2019.88  4921.8 2017.55  4936.6 2015.35  4947.2 2012.02  4953.1 2004.00
  4958.4 2004.28  4965.5 1994.67  4968.3 1990.88  4978.9 1968.65  4983.7 1966.60
  4984.2 1966.10  4995.6 1966.60  4997.4 1968.05  5021.4 1969.11  5032.1 1974.06
  5040.1 1976.43  5053.4 1978.13  5075.7 1977.28  5095.3 1973.89  5104.6 1974.14
  5138.9 1973.97  5211.0 1978.12  5301.7 1980.08  5388.7 1987.12  5427.2 1989.04
#Mann=7,-1,0
  4573.3   0.035       0  4838.0    0.07       0  4965.5     0.1       0
  4983.7    0.05       0  4995.6     0.1       0  5104.6    0.07       0
  5388.7     0.1       0
Bank Sta=4983.7,4995.6
Exp/Cntr=0.3,0.1

Type RM Length L Ch R = 1,6016,447,447,447
BEGIN DESCRIPTION:
Stream0165 11.0
END DESCRIPTION:
XS GIS Cut Line= 3
      1812225.00     13929475.00      1812125.00     13929325.00
      1812025.00     13929025.01
#Sta/Elev= 30
  4820.1 2006.73  4823.1 2006.73  4827.6 2005.53  4833.6 2004.82  4842.6 2002.13
  4848.6 2001.08  4856.2 1998.92  4878.7 1994.61  4928.3 1982.78  4964.3 1972.40
  4971.8 1966.65  4997.4 1963.99  5005.0 1963.90  5005.5 1963.40  5016.4 1963.40
  5016.9 1963.90  5021.5 1963.99  5032.0 1965.66  5042.5 1968.39  5053.1 1970.27
  5084.7 1972.59  5116.3 1973.79  5126.9 1974.72  5148.2 1974.94  5158.5 1974.76
  5190.1 1975.96  5232.3 1979.63  5263.9 1983.13  5285.0 1987.00  5316.6 1989.23
#Mann=4,-1,0
  4820.1    0.07       0  5005.0    0.05       0  5016.9    0.07       0
  5148.2    0.07       0
Bank Sta=5005,5016.9
Exp/Cntr=0.3,0.1

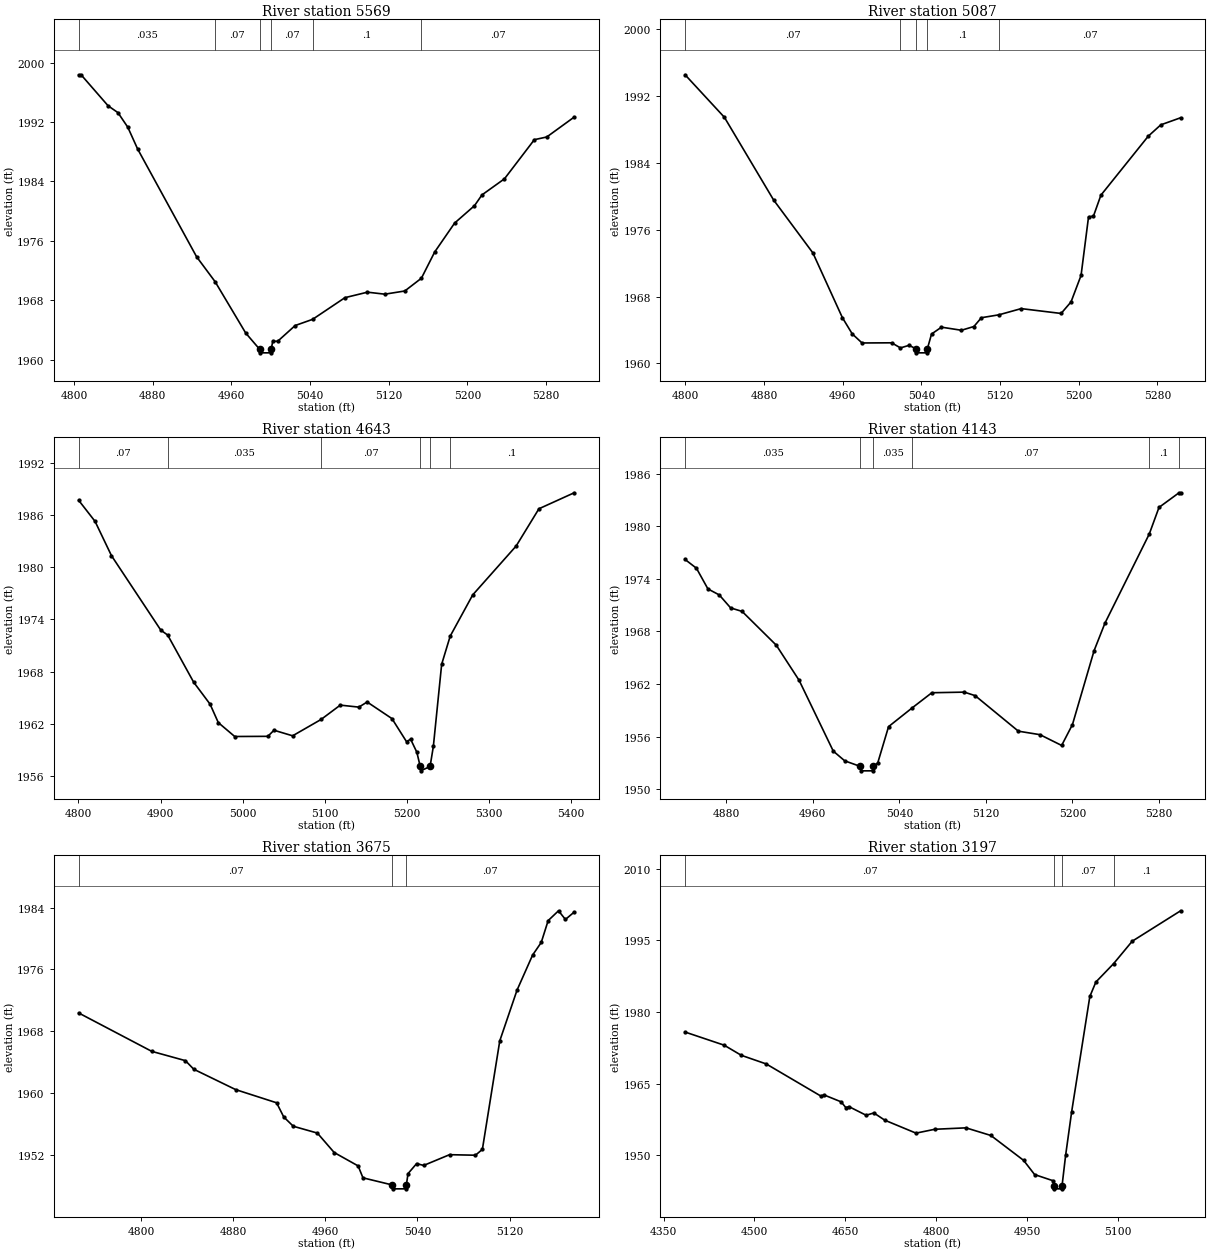
Type RM Length L Ch R = 1,5569,482,482,482
BEGIN DESCRIPTION:
Stream0165 10.0
END DESCRIPTION:
XS GIS Cut Line= 3
      1812525.00     13929374.98      1812525.00     13929175.00
      1812475.00     13928875.02
#Sta/Elev= 30
  4804.6 1998.36  4807.1 1998.36  4834.6 1994.18  4844.6 1993.26  4854.6 1991.30
  4864.6 1988.37  4924.6 1973.85  4943.5 1970.48  4974.6 1963.57  4988.6 1961.41
  4989.1 1960.91  5000.0 1960.91  5000.5 1961.41  5002.1 1962.47  5007.1 1962.47
  5024.9 1964.59  5042.6 1965.42  5075.5 1968.34  5098.4 1969.08  5116.1 1968.81
  5136.4 1969.24  5153.3 1970.96  5166.8 1974.49  5187.1 1978.39  5207.3 1980.73
  5214.9 1982.18  5237.8 1984.35  5268.2 1989.62  5280.8 1989.98  5308.7 1992.66
#Mann=6,-1,0
  4804.6   0.035       0  4943.5    0.07       0  4988.6    0.05       0
  5000.5    0.07       0  5042.6     0.1       0  5153.3    0.07       0
Bank Sta=4988.6,5000.5
Exp/Cntr=0.3,0.1

Type RM Length L Ch R = 1,5087,444,444,444
BEGIN DESCRIPTION:
Stream0165 9.0
END DESCRIPTION:
XS GIS Cut Line= 3
      1812975.00     13929274.99      1812975.00     13929075.00
      1812925.01     13928775.03
#Sta/Elev= 30
  4799.6 1994.53  4839.6 1989.44  4889.6 1979.56  4929.6 1973.22  4959.6 1965.48
  4969.6 1963.54  4979.6 1962.45  5009.7 1962.47  5018.7 1961.86  5027.5 1962.17
  5034.1 1961.77  5034.6 1961.27  5045.6 1961.27  5046.1 1961.77  5050.3 1963.52
  5060.4 1964.34  5080.7 1963.97  5093.4 1964.42  5101.0 1965.47  5118.9 1965.82
  5141.5 1966.56  5182.1 1965.98  5192.2 1967.36  5202.4 1970.53  5210.0 1977.53
  5215.0 1977.62  5222.6 1980.13  5270.8 1987.19  5283.5 1988.54  5303.7 1989.39
#Mann=5,-1,0
  4799.6    0.07       0  5018.7     0.1       0  5034.1    0.05       0
  5046.1     0.1       0  5118.9    0.07       0
Bank Sta=5034.1,5046.1
Exp/Cntr=0.3,0.1

Type RM Length L Ch R = 1,4643,500,500,500
BEGIN DESCRIPTION:
Stream0165 8.0
END DESCRIPTION:
XS GIS Cut Line= 3
      1813375.00     13929225.04      1813375.00     13929025.00
      1813425.01     13928624.96
#Sta/Elev= 30
  4800.3 1987.71  4820.3 1985.28  4840.3 1981.33  4900.3 1972.77  4908.7 1972.20
  4940.3 1966.78  4960.3 1964.25  4970.3 1962.13  4990.3 1960.53  5030.6 1960.55
  5038.1 1961.25  5060.8 1960.61  5095.4 1962.49  5118.8 1964.14  5141.4 1963.91
  5151.5 1964.50  5181.7 1962.59  5199.4 1959.94  5204.4 1960.22  5212.0 1958.72
  5216.1 1957.08  5216.6 1956.58  5228.1 1957.08  5232.1 1959.40  5242.2 1968.84
  5252.6 1972.08  5280.0 1976.82  5332.9 1982.45  5360.6 1986.73  5403.5 1988.57
#Mann=6,-1,0
  4800.3    0.07       0  4908.7   0.035       0  5095.4    0.07       0
  5216.1   0.035       0  5228.1    0.07       0  5252.6     0.1       0
Bank Sta=5216.1,5228.1
Exp/Cntr=0.3,0.1

Type RM Length L Ch R = 1,4143,468,468,468
BEGIN DESCRIPTION:
Stream0165 7.0
END DESCRIPTION:
XS GIS Cut Line= 3
      1813825.00     13929174.99      1813875.00     13929025.00
      1813875.00     13928725.00
#Sta/Elev= 30
  4841.9 1976.22  4852.4 1975.22  4863.0 1972.86  4873.5 1972.17  4884.0 1970.69
  4894.6 1970.29  4926.2 1966.43  4947.3 1962.42  4978.9 1954.33  4989.5 1953.22
  5004.0 1952.58  5004.5 1952.08  5015.5 1952.08  5016.0 1952.58  5020.0 1952.99
  5030.0 1957.13  5051.7 1959.26  5070.0 1961.00  5100.0 1961.07  5110.0 1960.67
  5150.0 1956.61  5170.0 1956.21  5190.0 1954.98  5200.0 1957.37  5220.0 1965.81
  5230.0 1968.94  5271.0 1979.13  5280.0 1982.17  5298.5 1983.84  5300.0 1983.84
#Mann=6,-1,0
  4841.9   0.035       0  5004.0   0.035       0  5016.0   0.035       0
  5051.7    0.07       0  5271.0     0.1       0  5298.5    0.07       0
Bank Sta=5004,5016
Exp/Cntr=0.3,0.1

Type RM Length L Ch R = 1,3675,478,478,478
BEGIN DESCRIPTION:
Stream0165 6.0
END DESCRIPTION:
XS GIS Cut Line= 3
      1814175.01     13929274.98      1814325.00     13929075.00
      1814425.02     13928924.96
#Sta/Elev= 30
  4745.8 1970.39  4809.3 1965.43  4838.5 1964.23  4845.8 1963.12  4882.2 1960.49
  4917.7 1958.79  4923.9 1956.96  4932.2 1955.76  4953.1 1954.88  4967.7 1952.37
  4988.5 1950.64  4992.7 1949.10  5018.2 1948.18  5018.7 1947.68  5029.9 1947.68
  5030.4 1948.18  5031.8 1949.64  5039.3 1950.94  5045.4 1950.70  5067.9 1952.09
  5090.4 1952.02  5096.4 1952.78  5111.5 1966.79  5126.5 1973.34  5140.0 1977.86
  5147.5 1979.49  5153.5 1982.31  5162.5 1983.58  5168.5 1982.46  5176.1 1983.41
#Mann=3,-1,0
  4745.8    0.07       0  5018.2    0.05       0  5030.4    0.07       0
Bank Sta=5018.2,5030.4
Exp/Cntr=0.3,0.1

Type RM Length L Ch R = 1,3197,454,454,454
BEGIN DESCRIPTION:
Stream0165 5.0
END DESCRIPTION:
XS GIS Cut Line= 3
      1814124.96     13929425.01      1814725.00     13929275.00
      1814924.99     13929275.00
#Sta/Elev= 30
  4385.4 1975.80  4449.9 1973.05  4478.2 1970.93  4519.4 1969.12  4609.6 1962.39
  4614.8 1962.63  4643.1 1961.18  4650.9 1959.97  4656.0 1960.18  4684.4 1958.37
  4697.2 1958.85  4715.3 1957.33  4766.8 1954.62  4797.8 1955.43  4849.3 1955.73
  4890.5 1954.13  4944.6 1948.91  4962.7 1945.94  4993.6 1944.63  4994.7 1943.45
  4995.2 1942.95  5007.4 1942.95  5007.9 1943.45  5013.9 1949.95  5023.9 1959.11
  5053.9 1983.25  5063.9 1986.28  5093.3 1990.15  5123.9 1994.83  5203.9 2001.21
#Mann=4,-1,0
  4385.4    0.07       0  4994.7    0.05       0  5007.9    0.07       0
  5093.3     0.1       0
Bank Sta=4994.7,5007.9
Exp/Cntr=0.3,0.1

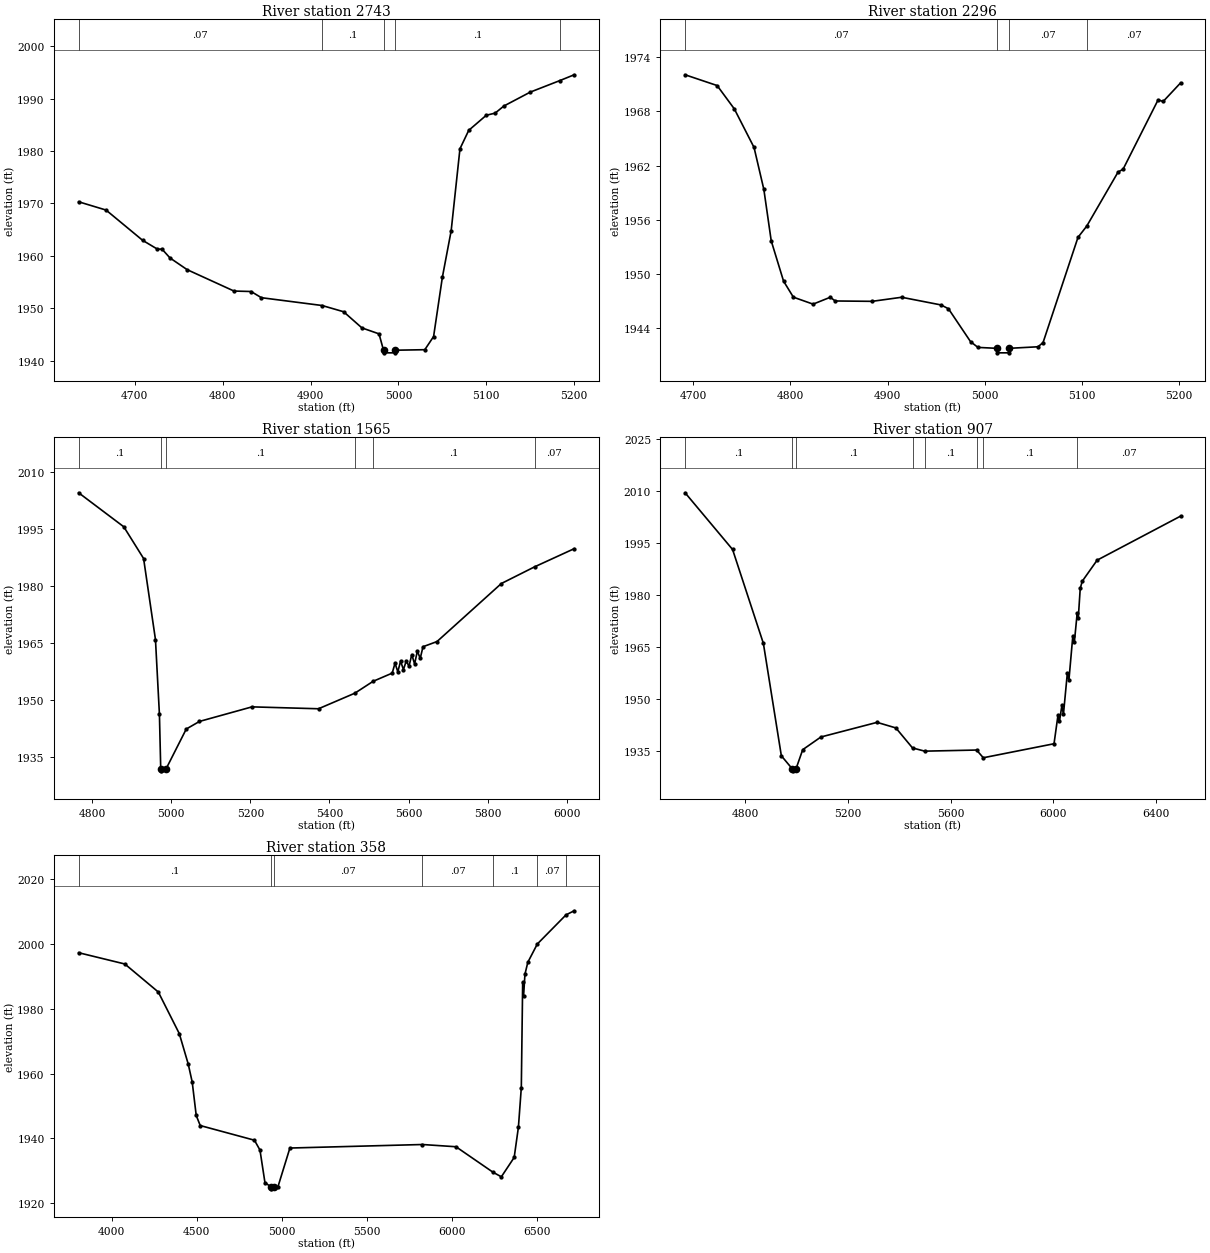
Type RM Length L Ch R = 1,2743,447,447,447
BEGIN DESCRIPTION:
Stream0165 4.0
END DESCRIPTION:
XS GIS Cut Line= 3
      1814225.00     13929575.00      1814575.00     13929675.00
      1814774.99     13929675.00
#Sta/Elev= 30
  4636.0 1970.31  4667.2 1968.73  4708.8 1962.96  4725.7 1961.27  4730.9 1961.28
  4740.0 1959.59  4759.5 1957.36  4812.8 1953.28  4832.3 1953.19  4844.0 1952.01
  4913.1 1950.52  4937.6 1949.33  4958.4 1946.25  4977.9 1945.11  4983.0 1941.99
  4983.5 1941.49  4995.7 1941.49  4996.2 1941.99  5030.0 1942.09  5040.0 1944.60
  5050.0 1955.92  5060.0 1964.78  5070.0 1980.42  5080.0 1983.94  5100.0 1986.82
  5110.0 1987.22  5120.0 1988.58  5150.0 1991.23  5183.8 1993.44  5200.0 1994.54
#Mann=5,-1,0
  4636.0    0.07       0  4913.1     0.1       0  4983.0    0.05       0
  4996.2     0.1       0  5183.8    0.07       0
Bank Sta=4983,4996.2
Exp/Cntr=0.3,0.1

Type RM Length L Ch R = 1,2296,731,731,731
BEGIN DESCRIPTION:
Stream0165 3.0
END DESCRIPTION:
XS GIS Cut Line= 3
      1814024.99     13929975.00      1814325.00     13930025.00
      1814525.00     13930075.00
#Sta/Elev= 30
  4691.5 1972.03  4724.5 1970.84  4742.2 1968.26  4762.5 1964.00  4772.6 1959.36
  4780.2 1953.68  4792.9 1949.23  4803.0 1947.46  4823.3 1946.69  4841.0 1947.45
  4846.1 1947.04  4884.1 1947.00  4914.5 1947.45  4955.1 1946.60  4962.7 1946.18
  4985.5 1942.54  4993.1 1941.91  5012.2 1941.81  5012.7 1941.31  5024.9 1941.31
  5025.4 1941.81  5054.9 1941.98  5060.1 1942.44  5096.1 1954.07  5105.1 1955.31
  5137.4 1961.29  5142.5 1961.59  5178.6 1969.26  5183.8 1969.08  5201.8 1971.14
#Mann=4,-1,0
  4691.5    0.07       0  5012.2    0.05       0  5025.4    0.07       0
  5105.1    0.07       0
Bank Sta=5012.2,5025.4
Exp/Cntr=0.3,0.1

Type RM Length L Ch R = 1,1565,658,658,658
BEGIN DESCRIPTION:
Stream0165 2.0
END DESCRIPTION:
XS GIS Cut Line= 4
      1813690.88     13930577.64      1813942.30     13930574.62
      1814289.46     13930502.74      1814750.67     13930050.64
#Sta/Elev= 30
  4766.3 2004.60  4880.4 1995.65  4930.4 1987.31  4960.4 1965.97  4970.4 1946.31
  4973.7 1931.95  4974.2 1931.45  4987.1 1931.95  5038.2 1942.45  5071.6 1944.45
  5204.3 1948.28  5372.3 1947.78  5464.1 1951.88  5510.2 1955.00  5558.5 1957.16
  5565.5 1959.77  5572.6 1957.51  5579.6 1960.29  5586.8 1958.09  5593.8 1960.31
  5600.9 1958.99  5607.9 1962.03  5615.0 1959.57  5622.0 1962.96  5629.2 1961.01
  5636.2 1964.10  5671.6 1965.46  5834.2 1980.73  5918.0 1985.11  6018.1 1989.89
#Mann=6,-1,0
  4766.3     0.1       0  4973.7    0.05       0  4987.1     0.1       0
  5464.1    0.07       0  5510.2     0.1       0  5918.0    0.07       0
Bank Sta=4973.7,4987.1
Exp/Cntr=0.3,0.1

Type RM Length L Ch R = 1,907,549,549,549
BEGIN DESCRIPTION:
Stream0165 1.0
END DESCRIPTION:
XS GIS Cut Line= 3
      1813740.04     13931115.41      1814175.00     13931125.00
      1814960.20     13929852.05
#Sta/Elev= 30
  4565.3 2009.49  4750.3 1993.10  4870.3 1965.96  4940.3 1933.48  4983.7 1929.63
  4984.2 1929.13  4997.1 1929.63  5023.5 1935.24  5094.4 1938.91  5313.2 1943.14
  5386.5 1941.53  5451.3 1935.75  5498.8 1934.82  5700.9 1935.14  5727.1 1932.91
  6002.7 1936.96  6018.1 1945.18  6023.9 1943.45  6033.5 1948.07  6039.3 1945.42
  6054.7 1957.46  6060.6 1955.27  6076.0 1968.17  6081.9 1966.31  6092.9 1974.67
  6097.3 1973.38  6104.8 1981.86  6112.7 1983.93  6170.6 1990.01  6496.0 2002.75
#Mann=8,-1,0
  4565.3     0.1       0  4983.7    0.05       0  4997.1     0.1       0
  5451.3    0.07       0  5498.8     0.1       0  5700.9    0.07       0
  5727.1     0.1       0  6092.9    0.07       0
Bank Sta=4983.7,4997.1
Exp/Cntr=0.3,0.1

Type RM Length L Ch R = 1,358,0,0,0
BEGIN DESCRIPTION:
Stream0165 0.0
END DESCRIPTION:
XS GIS Cut Line= 4
      1813515.36     13931983.18      1814532.01     13931546.34
      1814637.52     13931265.99      1815165.07     13929853.89
#Sta/Elev= 30
  3805.4 1997.35  4077.1 1993.86  4273.9 1985.20  4397.1 1972.36  4449.7 1962.95
  4473.2 1957.37  4496.8 1947.04  4520.3 1943.93  4839.0 1939.40  4871.6 1936.35
  4900.8 1926.31  4938.7 1924.87  4939.2 1924.37  4952.2 1924.87  4977.5 1925.05
  5047.5 1936.98  5827.1 1938.07  6023.9 1937.38  6242.0 1929.49  6290.7 1928.09
  6366.2 1934.07  6391.1 1943.44  6408.1 1955.66  6416.1 1988.15  6421.4 1983.96
  6429.5 1990.71  6446.4 1994.39  6502.2 2000.04  6671.1 2009.05  6718.9 2010.31
#Mann=7,-1,0
  3805.4     0.1       0  4938.7    0.05       0  4952.2    0.07       0
  5827.1    0.07       0  6242.0     0.1       0  6502.2    0.07       0
  6671.1   0.035       0
Bank Sta=4938.7,4952.2
Exp/Cntr=0.3,0.1

Chan Stop Cuts=-1