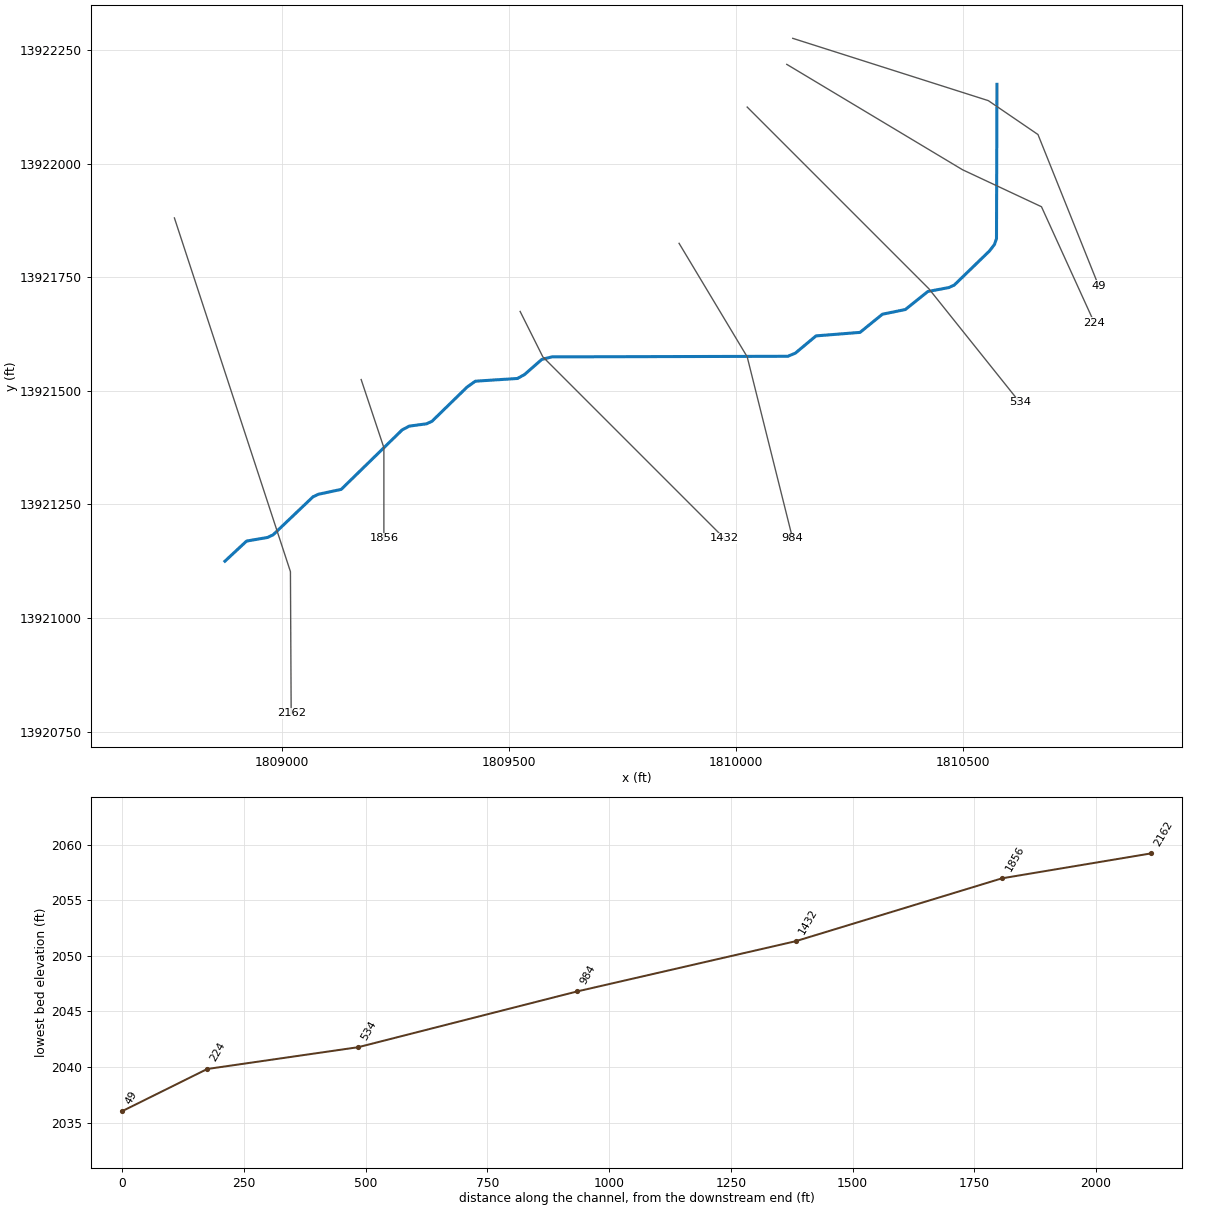
--- Stream0166.prj (project) ---

Proj Title=Stream0166 Base Level Engineering
Current Plan=p01
Default Exp/Contr=0.3,0.1
English Units
Geom File=g01
Flow File=f01
Plan File=p01
BEGIN DESCRIPTION:
Stream0166
END DESCRIPTION:

--- Stream0166.p01 (plan) ---

Plan Title=Multiple Run
Short Identifier=Multiple
Geom File=g01
Flow File=f01
Subcritical Flow
K Sum by GR= 0
Std Step Tol= 0.01
Critical Tol= 0.01
Num of Std Step Trials= 20
Max Error Tol= 0.3
Flow Tol Ratio= 0.001
Split Flow NTrial= 30
Split Flow Tol= 0.02
Split Flow Ratio= 0.02
Log Output Level= 0
Friction Slope Method= 1
Unsteady Friction Slope Method= 2
Unsteady Bridges Friction Slope Method= 1
Parabolic Critical Depth
Global Vel Dist=  1 , 1 , 1
Global Log Level= 0
CheckData=True
Encroach Param= -1, 0, 0, 0
BEGIN DESCRIPTION:
Multiple Run
END DESCRIPTION:

--- Stream0166.f01 (steady flow) ---

Flow Title=Multiple
Number of Profiles=7
Profile Names=10-year,25-year,50-year,1pct_min,100-year,1pct_plu,500-year
River Rch & RM= Stream0166,Reach-1,2162
    1510    2651    3766    2582    5152   10280    9541
Boundary for River Rch & Prof#=Stream0166,Reach-1,1
Up Type=0
Dn Type=3
Dn Slope=0.005
Boundary for River Rch & Prof#=Stream0166,Reach-1,2
Up Type=0
Dn Type=3
Dn Slope=0.005
Boundary for River Rch & Prof#=Stream0166,Reach-1,3
Up Type=0
Dn Type=3
Dn Slope=0.005
Boundary for River Rch & Prof#=Stream0166,Reach-1,4
Up Type=0
Dn Type=3
Dn Slope=0.005
Boundary for River Rch & Prof#=Stream0166,Reach-1,5
Up Type=0
Dn Type=3
Dn Slope=0.005
Boundary for River Rch & Prof#=Stream0166,Reach-1,6
Up Type=0
Dn Type=3
Dn Slope=0.005
Boundary for River Rch & Prof#=Stream0166,Reach-1,7
Up Type=0
Dn Type=3
Dn Slope=0.005

--- Stream0166.g01 (geometry) ---

Geom Title=Existing Conditions

River Reach=Stream0166,Reach-1
Reach XY= 30
      1808875.00     13921125.00      1808922.65     13921169.30
      1808969.03     13921177.35      1808981.08     13921183.07
      1809068.96     13921266.82      1809081.05     13921272.46
      1809131.05     13921283.16      1809265.32     13921414.22
      1809281.05     13921422.47      1809318.95     13921427.54
      1809331.04     13921433.18      1809408.26     13921508.51
      1809426.50     13921521.38      1809519.02     13921527.36
      1809534.63     13921535.90      1809572.66     13921569.26
      1809595.03     13921574.93      1810114.50     13921576.22
      1810131.06     13921583.14      1810176.60     13921621.14
      1810273.42     13921628.83      1810322.82     13921668.88
      1810373.28     13921679.16      1810422.82     13921718.90
      1810468.97     13921727.49      1810481.07     13921733.13
      1810558.58     13921808.20      1810569.55     13921822.53
      1810573.96     13921835.43      1810575.00     13922175.00

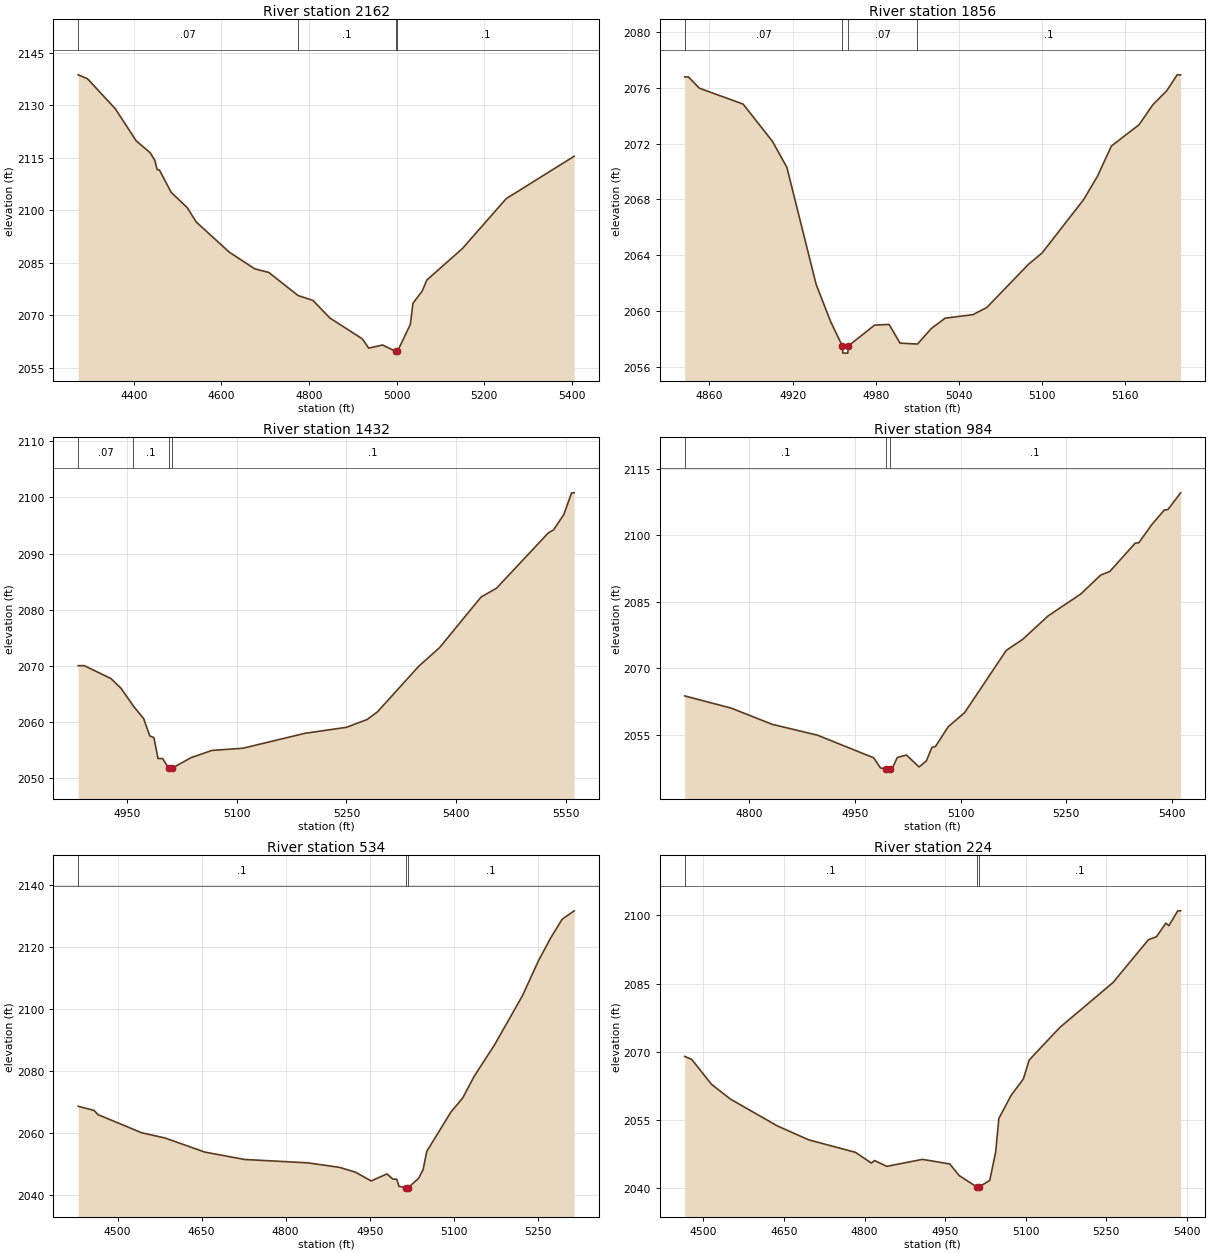
Type RM Length L Ch R = 1,2162,306,306,306
BEGIN DESCRIPTION:
Stream0166 5.0
END DESCRIPTION:
XS GIS Cut Line= 3
      1808763.75     13921880.88      1809019.24     13921102.01
      1809020.87     13920789.92
#Sta/Elev= 30
  4273.3 2138.64  4294.3 2137.55  4358.0 2128.95  4405.8 2119.78  4437.4 2116.42
  4447.9 2114.29  4453.5 2111.58  4458.7 2111.47  4485.3 2105.13  4522.4 2100.70
  4542.6 2096.64  4617.9 2088.05  4676.3 2083.26  4708.1 2082.25  4775.1 2075.64
  4808.8 2074.27  4847.8 2069.22  4921.5 2063.30  4936.2 2060.64  4968.0 2061.53
  4997.8 2059.71  4998.0 2059.21  5001.9 2059.71  5031.3 2067.42  5037.2 2073.43
  5058.2 2076.91  5068.8 2080.06  5150.0 2089.05  5250.0 2103.30  5405.1 2115.40
#Mann=4,-1,0
  4273.3    0.07       0  4775.1     0.1       0  4997.8    0.05       0
  5001.9     0.1       0
Bank Sta=4997.8,5001.9
Exp/Cntr=0.3,0.1

Type RM Length L Ch R = 1,1856,424,424,424
BEGIN DESCRIPTION:
Stream0166 4.0
END DESCRIPTION:
XS GIS Cut Line= 3
      1809174.99     13921525.02      1809225.00     13921375.00
      1809225.00     13921175.03
#Sta/Elev= 30
  4842.1 2076.79  4844.8 2076.79  4852.7 2075.98  4884.3 2074.84  4905.4 2072.18
  4915.9 2070.30  4937.0 2061.91  4947.5 2059.23  4956.0 2057.47  4956.3 2056.97
  4959.9 2056.97  4960.1 2057.47  4979.2 2058.98  4989.7 2059.03  4997.6 2057.69
  5010.2 2057.62  5020.2 2058.74  5030.2 2059.48  5050.2 2059.73  5060.2 2060.24
  5090.2 2063.33  5100.2 2064.16  5130.2 2067.99  5140.2 2069.67  5150.2 2071.83
  5170.2 2073.36  5180.2 2074.80  5190.2 2075.80  5197.7 2076.94  5200.2 2076.94
#Mann=4,-1,0
  4842.1    0.07       0  4956.0    0.05       0  4960.1    0.07       0
  5010.2     0.1       0
Bank Sta=4956,4960.1
Exp/Cntr=0.3,0.1

Type RM Length L Ch R = 1,1432,448,448,448
BEGIN DESCRIPTION:
Stream0166 3.0
END DESCRIPTION:
XS GIS Cut Line= 3
      1809525.02     13921674.96      1809575.00     13921575.00
      1809974.96     13921175.04
#Sta/Elev= 30
  4883.7 2070.07  4892.0 2070.07  4928.4 2067.78  4942.4 2066.01  4959.0 2062.90
  4973.1 2060.65  4981.5 2057.57  4987.1 2057.27  4992.7 2053.55  4999.0 2053.55
  5007.4 2051.81  5007.7 2051.31  5011.5 2051.31  5011.8 2051.81  5037.9 2053.71
  5066.2 2054.99  5108.6 2055.38  5193.5 2058.04  5250.0 2059.10  5278.3 2060.49
  5292.4 2061.85  5349.0 2069.99  5377.3 2073.28  5433.9 2082.27  5455.1 2083.85
  5525.8 2093.68  5532.9 2094.21  5547.0 2096.96  5557.6 2100.81  5561.1 2100.81
#Mann=4,-1,0
  4883.7    0.07       0  4959.0     0.1       0  5007.4    0.05       0
  5011.8     0.1       0
Bank Sta=5007.4,5011.8
Exp/Cntr=0.3,0.1

Type RM Length L Ch R = 1,984,450,450,450
BEGIN DESCRIPTION:
Stream0166 2.0
END DESCRIPTION:
XS GIS Cut Line= 3
      1809875.02     13921824.96      1810025.00     13921575.00
      1810125.00     13921175.01
#Sta/Elev= 30
  4708.4 2063.78  4774.4 2061.02  4832.7 2057.36  4896.9 2054.91  4976.6 2049.81
  4986.3 2047.51  4994.7 2047.30  4995.0 2046.80  4999.2 2047.30  5002.5 2047.30
  5010.2 2049.89  5023.1 2050.43  5041.1 2047.74  5051.4 2049.11  5059.2 2052.13
  5064.3 2052.36  5082.4 2056.83  5105.6 2059.99  5164.8 2074.06  5188.0 2076.53
  5224.1 2081.82  5270.5 2086.78  5298.8 2091.05  5311.7 2091.86  5347.8 2098.26
  5352.9 2098.34  5371.0 2102.38  5389.0 2105.73  5394.2 2105.84  5412.2 2109.61
#Mann=3,-1,0
  4708.4     0.1       0  4994.7    0.05       0  4999.2     0.1       0
Bank Sta=4994.7,4999.2
Exp/Cntr=0.3,0.1

Type RM Length L Ch R = 1,534,310,310,310
BEGIN DESCRIPTION:
Stream0166 1.0
END DESCRIPTION:
XS GIS Cut Line= 3
      1810025.00     13922125.00      1810425.00     13921725.00
      1810624.98     13921475.03
#Sta/Elev= 30
  4429.5 2068.55  4457.8 2067.21  4464.9 2065.85  4542.6 2060.01  4585.1 2058.27
  4655.8 2053.74  4726.5 2051.37  4839.6 2050.27  4896.2 2048.81  4924.5 2047.28
  4952.8 2044.42  4981.0 2046.70  4991.6 2045.00  4998.4 2045.00  5002.4 2042.69
  5014.5 2042.28  5014.8 2041.78  5019.1 2042.28  5037.6 2045.30  5045.6 2048.12
  5052.0 2053.96  5095.2 2066.69  5116.0 2071.17  5136.9 2078.29  5173.7 2088.58
  5223.3 2104.40  5251.3 2115.49  5272.9 2122.79  5293.7 2128.97  5315.3 2131.71
#Mann=3,-1,0
  4429.5     0.1       0  5014.5    0.05       0  5019.1     0.1       0
Bank Sta=5014.5,5019.1
Exp/Cntr=0.3,0.1

Type RM Length L Ch R = 1,224,175,175,175
BEGIN DESCRIPTION:
Stream0166 0.0
END DESCRIPTION:
XS GIS Cut Line= 4
      1810112.18     13922219.03      1810499.22     13921986.96
      1810673.03     13921905.52      1810789.25     13921650.36
#Sta/Elev= 30
  4465.0 2068.98  4478.3 2068.31  4514.9 2062.86  4549.9 2059.63  4637.7 2053.70
  4696.1 2050.65  4783.1 2047.90  4812.7 2045.55  4818.5 2046.10  4841.4 2044.83
  4907.9 2046.36  4958.8 2045.34  4976.1 2042.81  5008.7 2040.32  5009.0 2039.82
  5013.3 2040.32  5033.1 2041.73  5044.1 2047.92  5050.1 2055.34  5072.9 2060.42
  5095.7 2064.02  5106.6 2068.19  5163.7 2075.35  5262.6 2085.20  5328.6 2094.62
  5343.6 2095.28  5361.2 2098.27  5366.7 2097.71  5383.3 2100.97  5388.6 2100.97
#Mann=3,-1,0
  4465.0     0.1       0  5008.7    0.05       0  5013.3     0.1       0
Bank Sta=5008.7,5013.3
Exp/Cntr=0.3,0.1

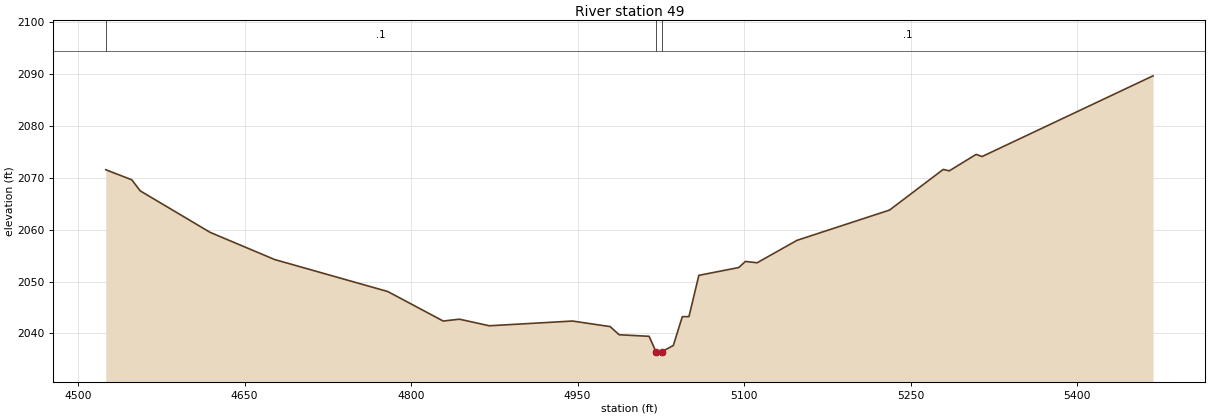
Type RM Length L Ch R = 1,49,0,0,0
BEGIN DESCRIPTION:
Stream0166 0.1
END DESCRIPTION:
XS GIS Cut Line= 4
      1810125.34     13922276.34      1810555.94     13922139.17
      1810665.31     13922064.52      1810799.00     13921731.16
#Sta/Elev= 30
  4525.0 2071.53  4548.4 2069.59  4556.1 2067.45  4619.1 2059.46  4677.2 2054.23
  4779.1 2048.07  4829.0 2042.39  4843.6 2042.75  4870.5 2041.48  4945.5 2042.39
  4979.4 2041.32  4987.5 2039.75  5014.5 2039.45  5020.6 2036.52  5021.1 2036.02
  5026.2 2036.52  5036.3 2037.68  5044.4 2043.23  5050.4 2043.25  5059.3 2051.19
  5095.2 2052.69  5101.3 2053.87  5111.8 2053.61  5147.7 2057.93  5231.1 2063.76
  5279.5 2071.59  5284.9 2071.31  5309.1 2074.48  5314.5 2074.07  5468.5 2089.61
#Mann=3,-1,0
  4525.0     0.1       0  5020.6    0.05       0  5026.2     0.1       0
Bank Sta=5020.6,5026.2
Exp/Cntr=0.3,0.1

Chan Stop Cuts=-1