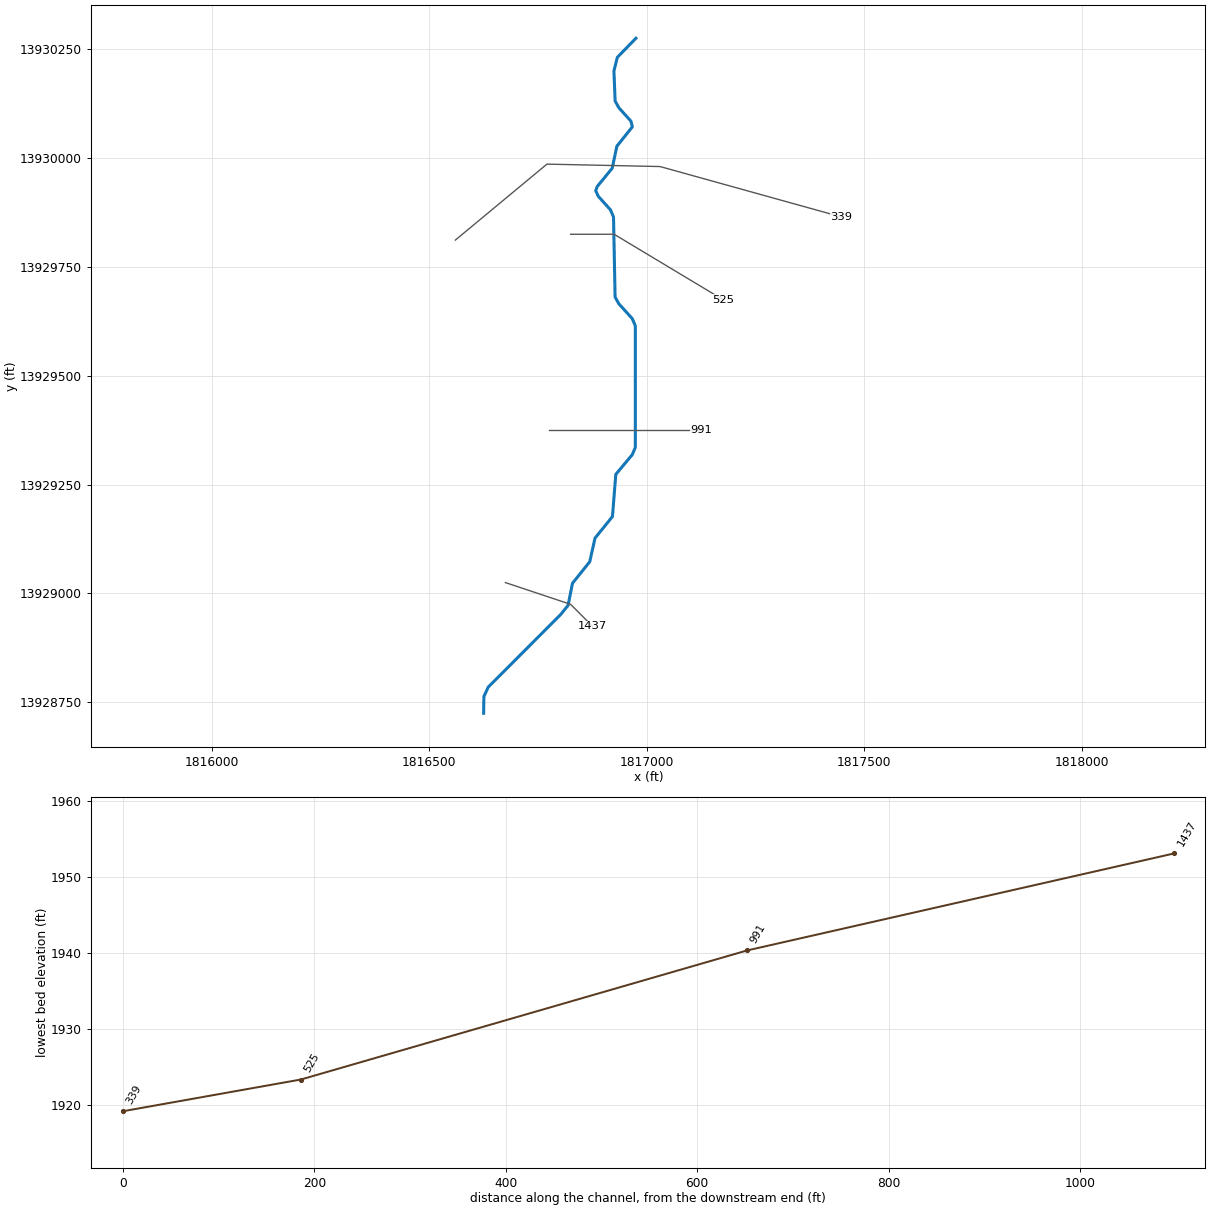
--- Stream0167.prj (project) ---

Proj Title=Stream0167 Base Level Engineering
Current Plan=p01
Default Exp/Contr=0.3,0.1
English Units
Geom File=g01
Flow File=f01
Plan File=p01
BEGIN DESCRIPTION:
Stream0167
END DESCRIPTION:

--- Stream0167.p01 (plan) ---

Plan Title=Multiple Run
Short Identifier=Multiple
Geom File=g01
Flow File=f01
Subcritical Flow
K Sum by GR= 0
Std Step Tol= 0.01
Critical Tol= 0.01
Num of Std Step Trials= 20
Max Error Tol= 0.3
Flow Tol Ratio= 0.001
Split Flow NTrial= 30
Split Flow Tol= 0.02
Split Flow Ratio= 0.02
Log Output Level= 0
Friction Slope Method= 1
Unsteady Friction Slope Method= 2
Unsteady Bridges Friction Slope Method= 1
Parabolic Critical Depth
Global Vel Dist=  1 , 1 , 1
Global Log Level= 0
CheckData=True
Encroach Param= -1, 0, 0, 0
BEGIN DESCRIPTION:
Multiple Run
END DESCRIPTION:

--- Stream0167.f01 (steady flow) ---

Flow Title=Multiple
Number of Profiles=7
Profile Names=10-year,25-year,50-year,1pct_min,100-year,1pct_plu,500-year
River Rch & RM= Stream0167,Reach-1,1437
     543     905    1243     829    1655    3302    2890
Boundary for River Rch & Prof#=Stream0167,Reach-1,1
Up Type=0
Dn Type=3
Dn Slope=0.005
Boundary for River Rch & Prof#=Stream0167,Reach-1,2
Up Type=0
Dn Type=3
Dn Slope=0.005
Boundary for River Rch & Prof#=Stream0167,Reach-1,3
Up Type=0
Dn Type=3
Dn Slope=0.005
Boundary for River Rch & Prof#=Stream0167,Reach-1,4
Up Type=0
Dn Type=3
Dn Slope=0.005
Boundary for River Rch & Prof#=Stream0167,Reach-1,5
Up Type=0
Dn Type=3
Dn Slope=0.005
Boundary for River Rch & Prof#=Stream0167,Reach-1,6
Up Type=0
Dn Type=3
Dn Slope=0.005
Boundary for River Rch & Prof#=Stream0167,Reach-1,7
Up Type=0
Dn Type=3
Dn Slope=0.005

--- Stream0167.g01 (geometry) ---

Geom Title=Existing Conditions

River Reach=Stream0167,Reach-1
Reach XY= 30
      1816625.00     13928725.00      1816625.59     13928763.16
      1816635.52     13928784.79      1816801.99     13928951.53
      1816819.17     13928972.70      1816829.19     13929023.26
      1816868.92     13929072.80      1816881.12     13929127.18
      1816921.17     13929176.58      1816928.86     13929273.40
      1816966.86     13929318.94      1816973.78     13929335.50
      1816973.78     13929614.50      1816966.86     13929631.06
      1816935.85     13929665.35      1816927.26     13929680.94
      1816923.62     13929864.56      1816916.54     13929881.19
      1816888.94     13929911.80      1816882.53     13929925.01
      1816886.42     13929934.93      1816920.61     13929976.65
      1816931.36     13930027.28      1816966.96     13930071.68
      1816963.54     13930084.90      1816936.17     13930115.22
      1816927.36     13930130.88      1816924.53     13930200.00
      1816932.36     13930231.32      1816975.00     13930275.00

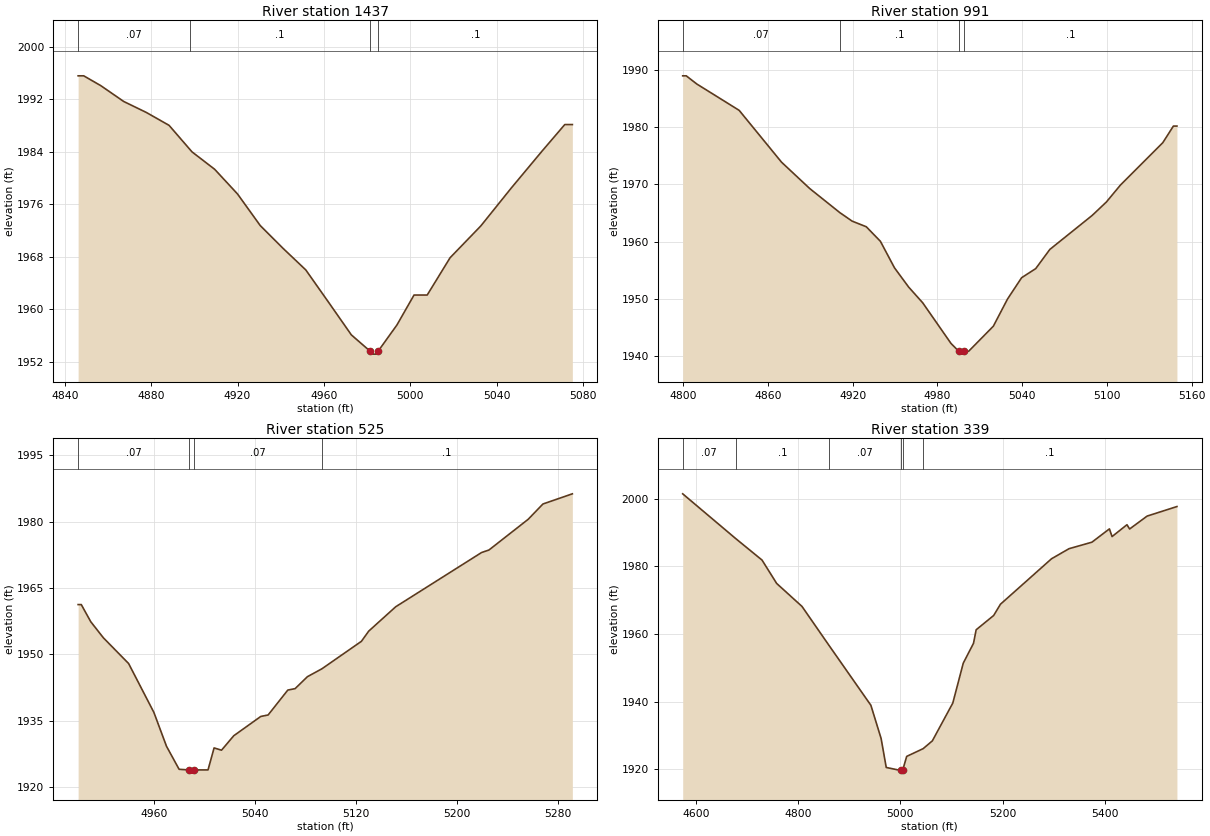
Type RM Length L Ch R = 1,1437,446,446,446
BEGIN DESCRIPTION:
Stream0167 3.0
END DESCRIPTION:
XS GIS Cut Line= 3
      1816675.01     13929025.00      1816825.00     13928975.00
      1816874.99     13928925.01
#Sta/Elev= 29
  4846.2 1995.59  4848.8 1995.59  4856.7 1994.09  4867.3 1991.68  4877.8 1990.00
  4888.3 1988.04  4897.8 1984.42  4898.9 1984.00  4909.4 1981.34  4920.0 1977.57
  4930.5 1972.76  4941.1 1969.27  4951.6 1965.99  4962.1 1961.08  4972.7 1956.08
  4981.2 1953.65  4981.5 1953.15  4985.0 1953.15  4985.2 1953.65  4993.8 1957.60
  5001.7 1962.16  5004.3 1962.16  5007.8 1962.16  5018.4 1967.85  5032.6 1972.69
  5046.7 1978.47  5060.9 1984.08  5071.5 1988.16  5075.0 1988.16
#Mann=4,-1,0
  4846.2    0.07       0  4897.8     0.1       0  4981.2    0.05       0
  4985.2     0.1       0
Bank Sta=4981.2,4985.2
Exp/Cntr=0.3,0.1

Type RM Length L Ch R = 1,991,466,466,466
BEGIN DESCRIPTION:
Stream0167 2.0
END DESCRIPTION:
XS GIS Cut Line= 3
      1816775.01     13929375.00      1816975.00     13929375.00
      1817125.01     13929375.00
#Sta/Elev= 30
  4799.6 1988.96  4802.1 1988.96  4809.6 1987.53  4839.6 1982.93  4869.6 1973.88
  4889.6 1969.27  4910.8 1965.09  4919.6 1963.59  4929.6 1962.61  4939.6 1960.07
  4949.6 1955.43  4959.6 1952.08  4969.6 1949.32  4989.6 1942.24  4995.1 1940.87
  4995.3 1940.37  4998.8 1940.37  4999.1 1940.87  5002.1 1940.87  5019.6 1945.25
  5029.6 1949.98  5039.6 1953.71  5049.6 1955.30  5059.6 1958.65  5089.6 1964.59
  5099.6 1966.92  5109.6 1969.89  5139.6 1977.29  5147.1 1980.19  5149.6 1980.19
#Mann=4,-1,0
  4799.6    0.07       0  4910.8     0.1       0  4995.1    0.05       0
  4999.1     0.1       0
Bank Sta=4995.1,4999.1
Exp/Cntr=0.3,0.1

Type RM Length L Ch R = 1,525,186,186,186
BEGIN DESCRIPTION:
Stream0167 1.0
END DESCRIPTION:
XS GIS Cut Line= 3
      1816825.03     13929825.00      1816925.00     13929825.00
      1817174.98     13929675.01
#Sta/Elev= 30
  4899.6 1961.25  4902.1 1961.25  4909.6 1957.38  4919.6 1953.74  4939.6 1947.92
  4959.6 1936.88  4969.6 1929.22  4979.6 1924.01  4987.6 1923.87  4987.8 1923.37
  4991.3 1923.37  4991.6 1923.87  5002.5 1923.87  5007.3 1928.84  5013.2 1928.33
  5022.9 1931.60  5044.3 1935.96  5050.1 1936.29  5065.7 1941.92  5071.5 1942.25
  5081.2 1944.94  5092.7 1946.73  5124.0 1952.94  5129.8 1955.25  5151.2 1960.76
  5219.2 1973.02  5225.0 1973.58  5256.1 1980.53  5267.8 1983.99  5291.1 1986.29
#Mann=4,-1,0
  4899.6    0.07       0  4987.6    0.05       0  4991.6    0.07       0
  5092.7     0.1       0
Bank Sta=4987.6,4991.6
Exp/Cntr=0.3,0.1

Type RM Length L Ch R = 1,339,0,0,0
BEGIN DESCRIPTION:
Stream0167 0.0
END DESCRIPTION:
XS GIS Cut Line= 4
      1816559.97     13929811.60      1816770.57     13929986.07
      1817030.68     13929980.50      1817447.46     13929864.76
#Sta/Elev= 30
  4574.5 2001.42  4678.1 1988.20  4729.6 1981.84  4758.2 1974.94  4807.7 1968.15
  4861.1 1956.51  4942.4 1938.94  4962.4 1929.11  4972.4 1920.57  5000.4 1919.69
  5000.7 1919.19  5004.4 1919.69  5012.4 1923.84  5044.5 1926.12  5062.5 1928.42
  5102.5 1939.59  5123.0 1951.40  5143.0 1957.25  5148.2 1961.25  5182.4 1965.47
  5195.7 1968.80  5295.6 1982.24  5329.8 1985.21  5374.5 1987.13  5408.7 1991.06
  5413.9 1988.79  5443.0 1992.29  5448.2 1991.03  5482.4 1994.84  5540.7 1997.66
#Mann=6,-1,0
  4574.5    0.07       0  4678.1     0.1       0  4861.1    0.07       0
  5000.4    0.05       0  5004.4    0.07       0  5044.5     0.1       0
Bank Sta=5000.4,5004.4
Exp/Cntr=0.3,0.1

Chan Stop Cuts=-1