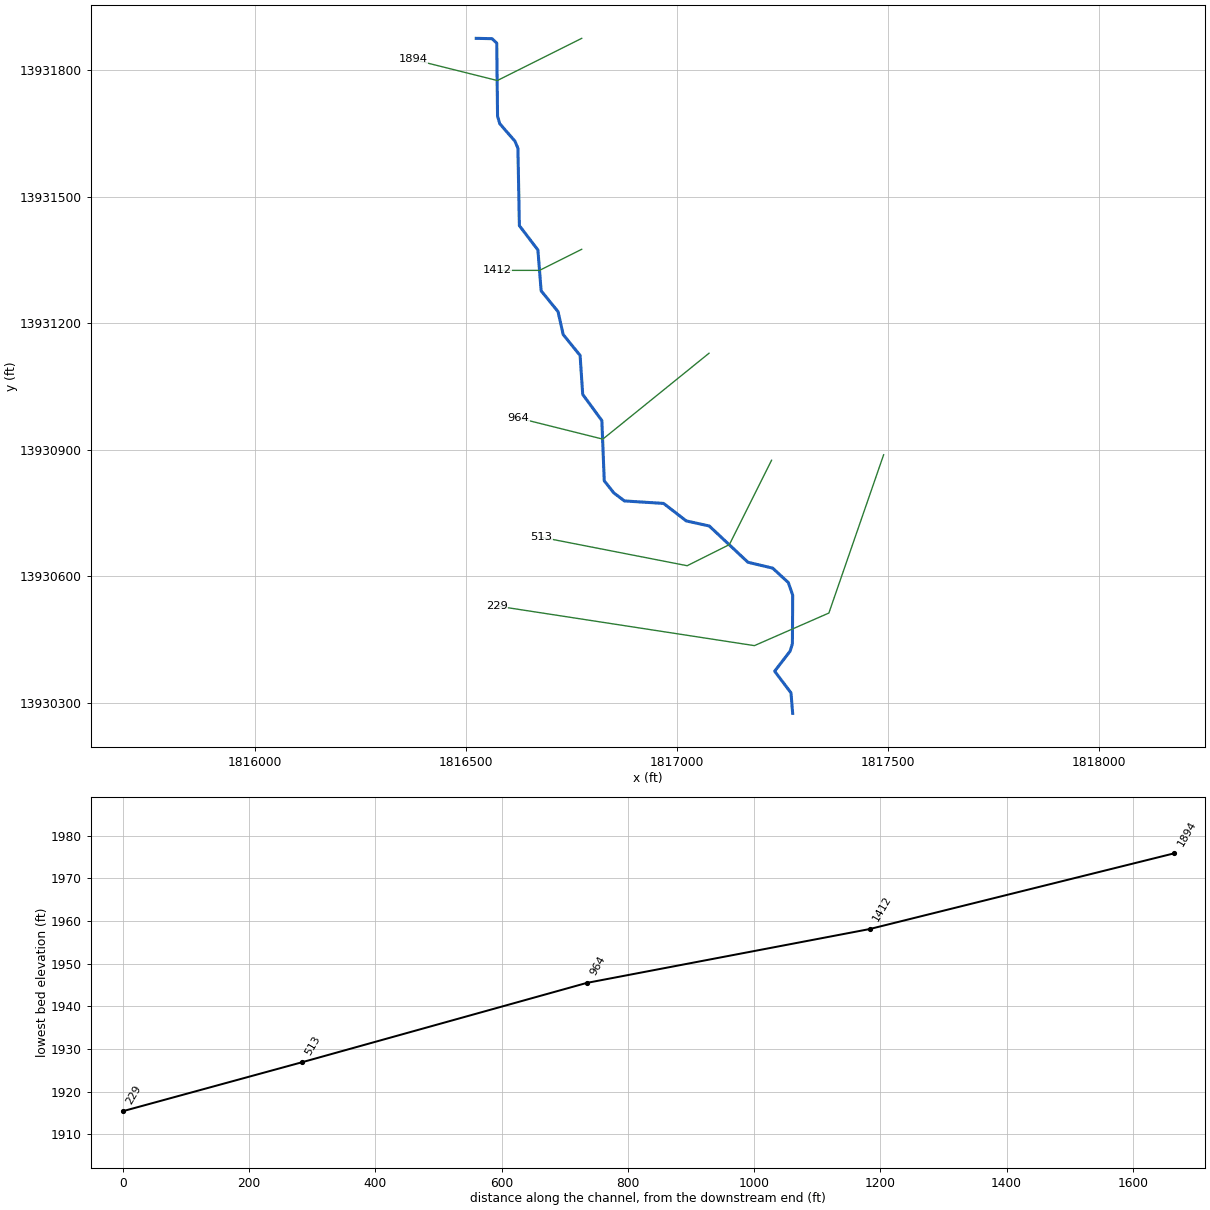
--- Stream0168.prj (project) ---

Proj Title=Stream0168 Base Level Engineering
Current Plan=p01
Default Exp/Contr=0.3,0.1
English Units
Geom File=g01
Flow File=f01
Plan File=p01
BEGIN DESCRIPTION:
Stream0168
END DESCRIPTION:

--- Stream0168.p01 (plan) ---

Plan Title=Multiple Run
Short Identifier=Multiple
Geom File=g01
Flow File=f01
Subcritical Flow
K Sum by GR= 0
Std Step Tol= 0.01
Critical Tol= 0.01
Num of Std Step Trials= 20
Max Error Tol= 0.3
Flow Tol Ratio= 0.001
Split Flow NTrial= 30
Split Flow Tol= 0.02
Split Flow Ratio= 0.02
Log Output Level= 0
Friction Slope Method= 1
Unsteady Friction Slope Method= 2
Unsteady Bridges Friction Slope Method= 1
Parabolic Critical Depth
Global Vel Dist=  1 , 1 , 1
Global Log Level= 0
CheckData=True
Encroach Param= -1, 0, 0, 0
BEGIN DESCRIPTION:
Multiple Run
END DESCRIPTION:

--- Stream0168.f01 (steady flow) ---

Flow Title=Multiple
Number of Profiles=7
Profile Names=10-year,25-year,50-year,1pct_min,100-year,1pct_plu,500-year
River Rch & RM= Stream0168,Reach-1,1894
     347     555     741     481     960    1915    1583
Boundary for River Rch & Prof#=Stream0168,Reach-1,1
Up Type=0
Dn Type=3
Dn Slope=0.005
Boundary for River Rch & Prof#=Stream0168,Reach-1,2
Up Type=0
Dn Type=3
Dn Slope=0.005
Boundary for River Rch & Prof#=Stream0168,Reach-1,3
Up Type=0
Dn Type=3
Dn Slope=0.005
Boundary for River Rch & Prof#=Stream0168,Reach-1,4
Up Type=0
Dn Type=3
Dn Slope=0.005
Boundary for River Rch & Prof#=Stream0168,Reach-1,5
Up Type=0
Dn Type=3
Dn Slope=0.005
Boundary for River Rch & Prof#=Stream0168,Reach-1,6
Up Type=0
Dn Type=3
Dn Slope=0.005
Boundary for River Rch & Prof#=Stream0168,Reach-1,7
Up Type=0
Dn Type=3
Dn Slope=0.005

--- Stream0168.g01 (geometry) ---

Geom Title=Existing Conditions

River Reach=Stream0168,Reach-1
Reach XY= 30
      1816525.00     13931875.00      1816562.57     13931874.17
      1816573.57     13931863.57      1816575.52     13931690.22
      1816580.75     13931672.67      1816616.86     13931631.06
      1816623.78     13931614.49      1816627.26     13931430.94
      1816671.14     13931373.40      1816678.83     13931276.58
      1816718.89     13931227.18      1816731.11     13931172.82
      1816771.17     13931123.42      1816777.36     13931030.98
      1816822.73     13930969.06      1816828.44     13930826.23
      1816850.98     13930797.67      1816876.25     13930778.51
      1816969.03     13930772.66      1817022.83     13930731.14
      1817077.29     13930719.16      1817168.98     13930633.19
      1817227.58     13930619.26      1817264.66     13930585.12
      1817275.10     13930555.11      1817274.37     13930440.17
      1817269.01     13930422.55      1817232.31     13930374.96
      1817271.00     13930323.64      1817275.00     13930275.00

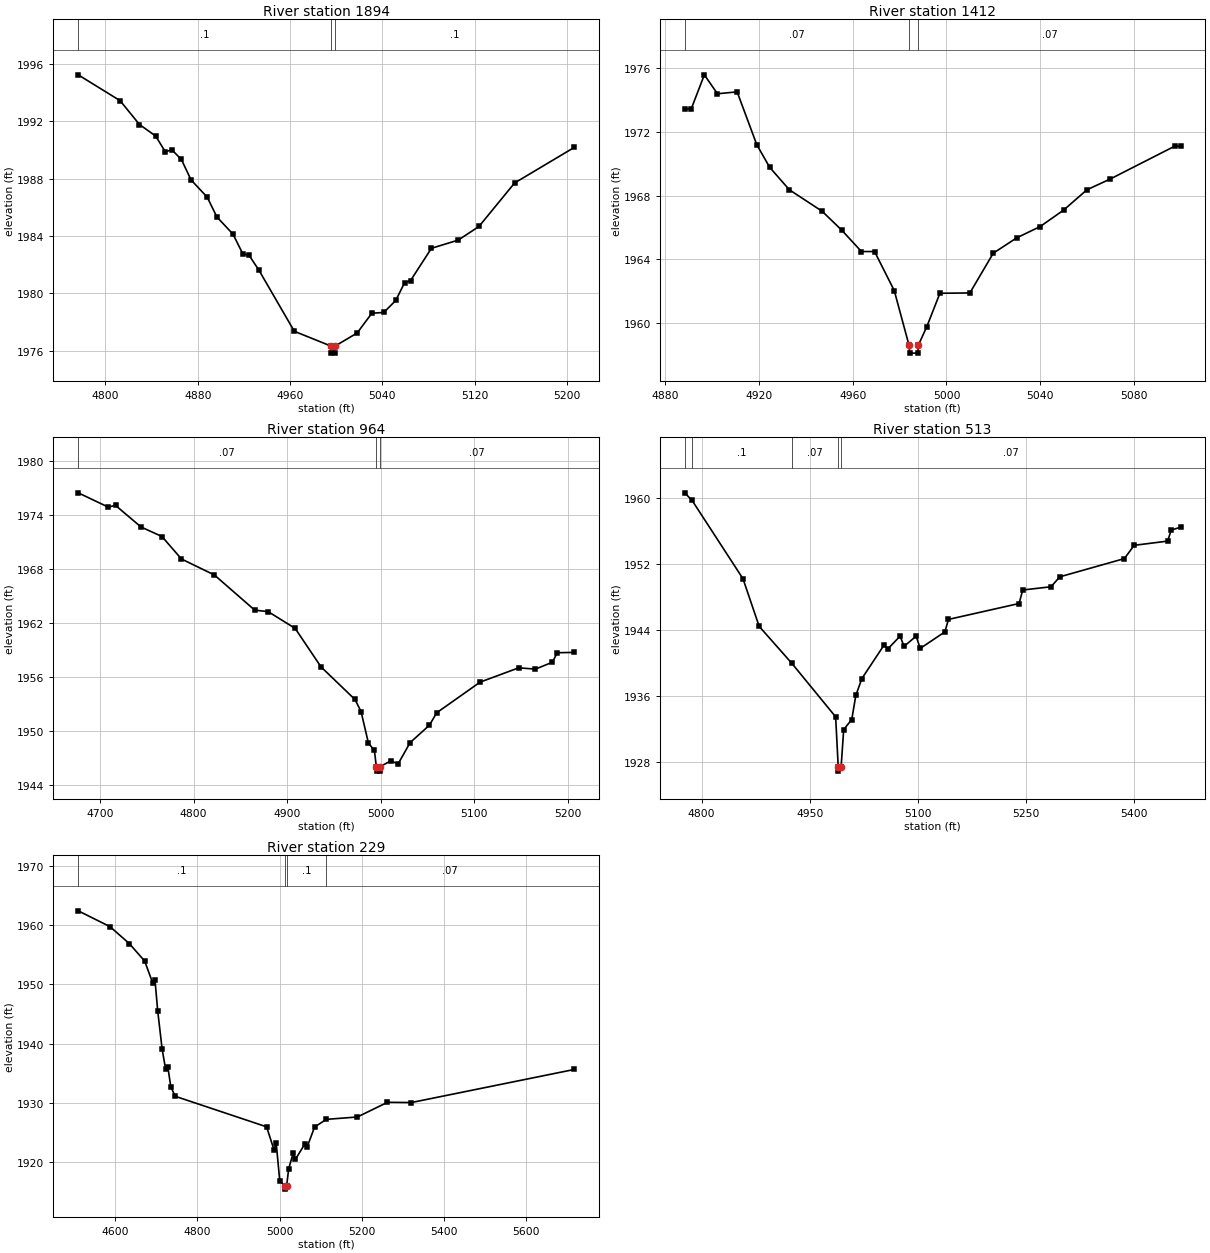
Type RM Length L Ch R = 1,1894,482,482,482
BEGIN DESCRIPTION:
Stream0168 4.0
END DESCRIPTION:
XS GIS Cut Line= 3
      1816775.01     13931875.00      1816575.00     13931775.00
      1816374.97     13931825.01
#Sta/Elev= 30
  4776.4 1995.22  4812.7 1993.42  4829.5 1991.76  4843.5 1990.96  4851.9 1989.86
  4857.5 1990.00  4865.8 1989.33  4874.2 1987.90  4888.2 1986.70  4896.6 1985.32
  4910.6 1984.12  4919.0 1982.76  4924.5 1982.65  4932.9 1981.63  4963.7 1977.36
  4995.2 1976.34  4995.5 1975.84  4999.0 1975.84  4999.2 1976.34  5018.1 1977.24
  5030.9 1978.62  5041.2 1978.67  5051.6 1979.51  5059.3 1980.75  5064.4 1980.89
  5082.5 1983.14  5105.7 1983.71  5123.7 1984.66  5154.6 1987.69  5206.2 1990.16
#Mann=3,-1,0
  4776.4     0.1       0  4995.2    0.05       0  4999.2     0.1       0
Bank Sta=4995.2,4999.2
Exp/Cntr=0.3,0.1

Type RM Length L Ch R = 1,1412,448,448,448
BEGIN DESCRIPTION:
Stream0168 3.0
END DESCRIPTION:
XS GIS Cut Line= 3
      1816775.01     13931375.00      1816675.00     13931325.00
      1816575.01     13931325.00
#Sta/Elev= 28
  4888.2 1973.45  4891.0 1973.45  4896.6 1975.59  4902.2 1974.40  4910.6 1974.52
  4919.0 1971.20  4924.5 1969.78  4932.9 1968.37  4946.9 1967.02  4955.3 1965.83
  4963.7 1964.49  4969.3 1964.49  4977.7 1962.04  4984.0 1958.61  4984.3 1958.11
  4987.8 1958.11  4988.0 1958.61  4991.6 1959.77  4997.2 1961.87  5010.0 1961.89
  5020.0 1964.39  5030.0 1965.35  5040.0 1966.06  5050.0 1967.09  5060.0 1968.37
  5070.0 1969.05  5097.5 1971.11  5100.0 1971.11
#Mann=3,-1,0
  4888.2    0.07       0  4984.0    0.05       0  4988.0    0.07       0
Bank Sta=4984,4988
Exp/Cntr=0.3,0.1

Type RM Length L Ch R = 1,964,451,451,451
BEGIN DESCRIPTION:
Stream0168 2.0
END DESCRIPTION:
XS GIS Cut Line= 3
      1817076.70     13931128.58      1816825.00     13930925.00
      1816624.98     13930975.01
#Sta/Elev= 30
  4676.7 1976.45  4708.6 1974.87  4716.6 1975.05  4743.8 1972.65  4766.2 1971.59
  4787.0 1969.09  4822.2 1967.31  4865.3 1963.40  4879.7 1963.23  4908.5 1961.37
  4936.1 1957.09  4972.4 1953.46  4978.9 1952.12  4986.8 1948.60  4993.2 1947.79
  4995.2 1945.99  4995.5 1945.49  4999.0 1945.49  4999.2 1945.99  5010.7 1946.63
  5018.5 1946.29  5031.3 1948.66  5052.0 1950.60  5059.7 1951.98  5106.1 1955.39
  5147.3 1956.98  5165.3 1956.84  5183.4 1957.61  5188.5 1958.66  5206.6 1958.70
#Mann=3,-1,0
  4676.7    0.07       0  4995.2    0.05       0  4999.2    0.07       0
Bank Sta=4995.2,4999.2
Exp/Cntr=0.3,0.1

Type RM Length L Ch R = 1,513,284,284,284
BEGIN DESCRIPTION:
Stream0168 1.0
END DESCRIPTION:
XS GIS Cut Line= 4
      1817224.99     13930874.98      1817125.00     13930675.00
      1817025.00     13930625.00      1816678.34     13930692.70
#Sta/Elev= 30
  4776.4 1960.67  4786.6 1959.76  4857.4 1950.24  4879.8 1944.47  4925.0 1940.00
  4986.0 1933.49  4989.6 1927.40  4989.9 1926.90  4993.6 1927.40  4997.2 1931.95
  5008.4 1933.16  5014.0 1936.08  5022.4 1938.13  5053.1 1942.18  5058.7 1941.75
  5075.5 1943.28  5081.0 1942.04  5097.8 1943.28  5103.4 1941.79  5137.6 1943.79
  5142.7 1945.31  5240.7 1947.24  5245.8 1948.88  5285.0 1949.27  5297.3 1950.48
  5386.9 1952.69  5400.5 1954.30  5446.9 1954.81  5452.0 1956.15  5465.0 1956.50
#Mann=5,-1,0
  4776.4    0.07       0  4786.6     0.1       0  4925.0    0.07       0
  4989.6    0.05       0  4993.6    0.07       0
Bank Sta=4989.6,4993.6
Exp/Cntr=0.3,0.1

Type RM Length L Ch R = 1,229,0,0,0
BEGIN DESCRIPTION:
Stream0168 0.0
END DESCRIPTION:
XS GIS Cut Line= 4
      1817490.63     13930888.00      1817360.82     13930512.80
      1817184.36     13930435.58      1816573.57     13930529.49
#Sta/Elev= 30
  4509.8 1962.41  4587.0 1959.75  4634.4 1956.87  4671.7 1953.92  4691.4 1950.18
  4696.7 1950.75  4703.4 1945.49  4714.0 1939.14  4722.6 1935.66  4727.9 1936.12
  4735.2 1932.73  4745.8 1931.10  4968.5 1925.94  4986.4 1922.09  4991.8 1923.25
  5000.5 1916.86  5013.2 1915.92  5013.5 1915.42  5017.2 1915.92  5022.3 1918.87
  5033.2 1921.49  5038.6 1920.44  5062.0 1923.08  5067.5 1922.58  5085.4 1925.91
  5114.0 1927.20  5189.5 1927.60  5262.9 1930.08  5321.1 1930.04  5717.4 1935.62
#Mann=4,-1,0
  4509.8     0.1       0  5013.2    0.05       0  5017.2     0.1       0
  5114.0    0.07       0
Bank Sta=5013.2,5017.2
Exp/Cntr=0.3,0.1

Chan Stop Cuts=-1