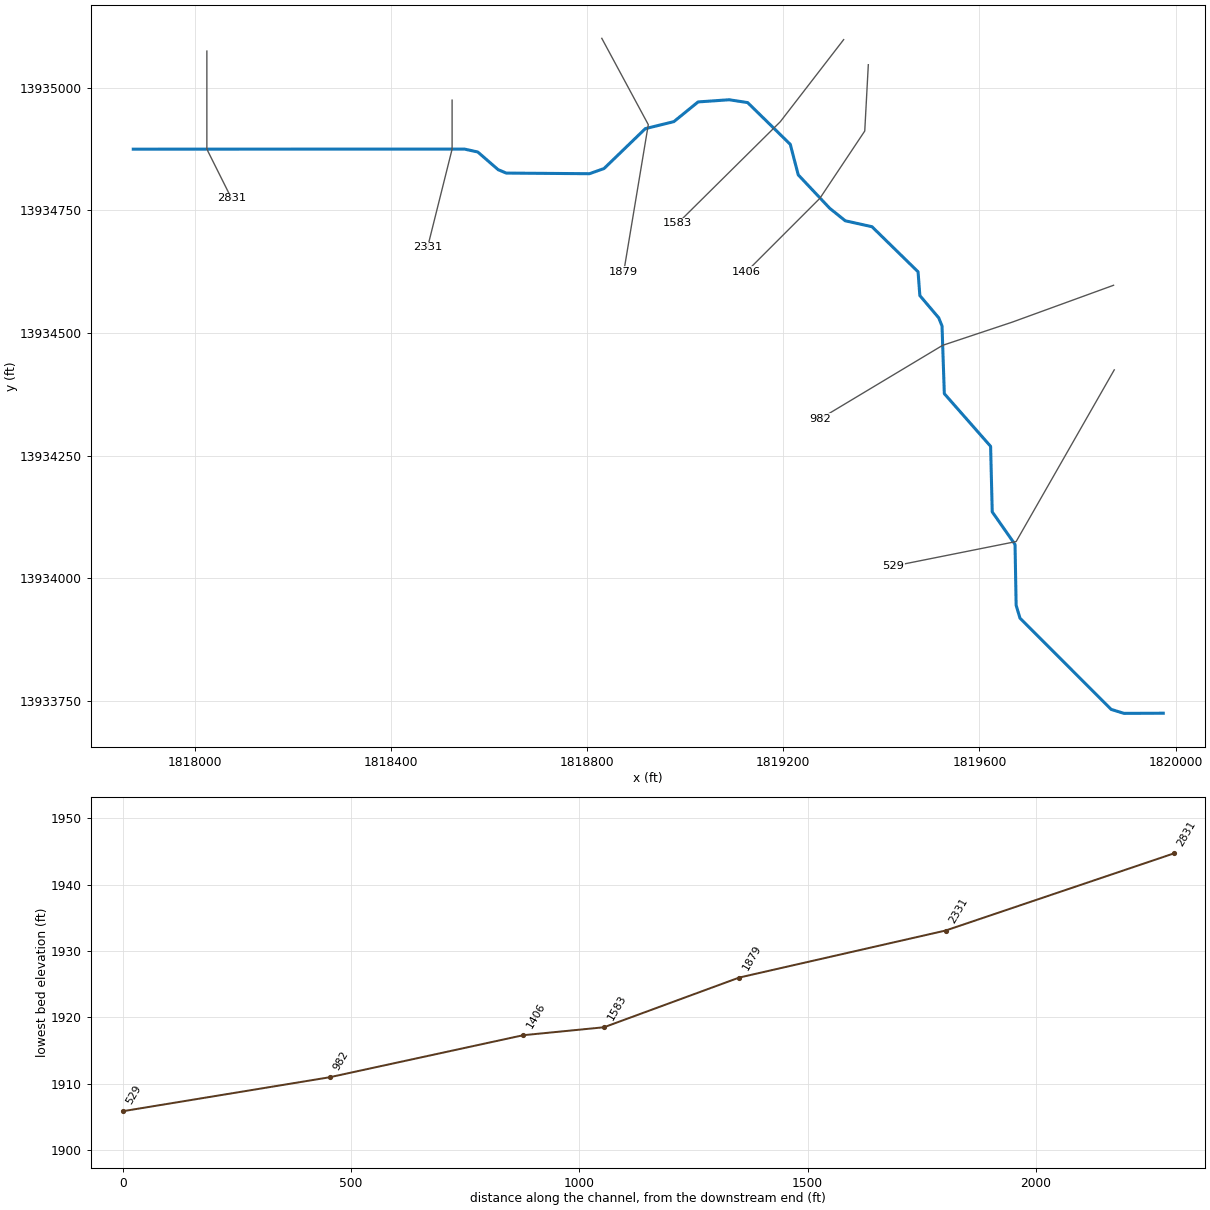
--- Stream0169.prj (project) ---

Proj Title=Stream0169 Base Level Engineering
Current Plan=p01
Default Exp/Contr=0.3,0.1
English Units
Geom File=g01
Flow File=f01
Plan File=p01
BEGIN DESCRIPTION:
Stream0169
END DESCRIPTION:

--- Stream0169.p01 (plan) ---

Plan Title=Multiple Run
Short Identifier=Multiple
Geom File=g01
Flow File=f01
Subcritical Flow
K Sum by GR= 0
Std Step Tol= 0.01
Critical Tol= 0.01
Num of Std Step Trials= 20
Max Error Tol= 0.3
Flow Tol Ratio= 0.001
Split Flow NTrial= 30
Split Flow Tol= 0.02
Split Flow Ratio= 0.02
Log Output Level= 0
Friction Slope Method= 1
Unsteady Friction Slope Method= 2
Unsteady Bridges Friction Slope Method= 1
Parabolic Critical Depth
Global Vel Dist=  1 , 1 , 1
Global Log Level= 0
CheckData=True
Encroach Param= -1, 0, 0, 0
BEGIN DESCRIPTION:
Multiple Run
END DESCRIPTION:

--- Stream0169.f01 (steady flow) ---

Flow Title=Multiple
Number of Profiles=7
Profile Names=10-year,25-year,50-year,1pct_min,100-year,1pct_plu,500-year
River Rch & RM= Stream0169,Reach-1,2831
     813    1382    1921    1293    2580    5147    4597
River Rch & RM= Stream0169,Reach-1,1583
    1326    2326    3301    2265    4520    9019    8379
River Rch & RM= Stream0169,Reach-1,982
    1544    2730    3896    2686    5360   10694   10031
Boundary for River Rch & Prof#=Stream0169,Reach-1,1
Up Type=0
Dn Type=3
Dn Slope=0.005
Boundary for River Rch & Prof#=Stream0169,Reach-1,2
Up Type=0
Dn Type=3
Dn Slope=0.005
Boundary for River Rch & Prof#=Stream0169,Reach-1,3
Up Type=0
Dn Type=3
Dn Slope=0.005
Boundary for River Rch & Prof#=Stream0169,Reach-1,4
Up Type=0
Dn Type=3
Dn Slope=0.005
Boundary for River Rch & Prof#=Stream0169,Reach-1,5
Up Type=0
Dn Type=3
Dn Slope=0.005
Boundary for River Rch & Prof#=Stream0169,Reach-1,6
Up Type=0
Dn Type=3
Dn Slope=0.005
Boundary for River Rch & Prof#=Stream0169,Reach-1,7
Up Type=0
Dn Type=3
Dn Slope=0.005

--- Stream0169.g01 (geometry) ---

Geom Title=Existing Conditions

River Reach=Stream0169,Reach-1
Reach XY= 30
      1817875.00     13934875.00      1818550.08     13934875.20
      1818577.33     13934869.25      1818618.94     13934833.14
      1818635.51     13934826.22      1818805.02     13934824.96
      1818834.79     13934835.50      1818918.95     13934916.84
      1818977.17     13934931.14      1819026.57     13934971.33
      1819090.04     13934975.73      1819127.55     13934969.95
      1819214.50     13934884.79      1819230.71     13934822.64
      1819294.77     13934754.58      1819326.63     13934728.96
      1819381.07     13934716.89      1819475.00     13934625.00
      1819478.65     13934576.51      1819517.10     13934531.16
      1819523.87     13934514.53      1819528.56     13934376.47
      1819622.92     13934269.14      1819626.23     13934135.51
      1819672.73     13934069.06      1819674.98     13933944.99
      1819682.82     13933918.81      1819868.78     13933732.74
      1819894.86     13933724.67      1819975.00     13933725.00

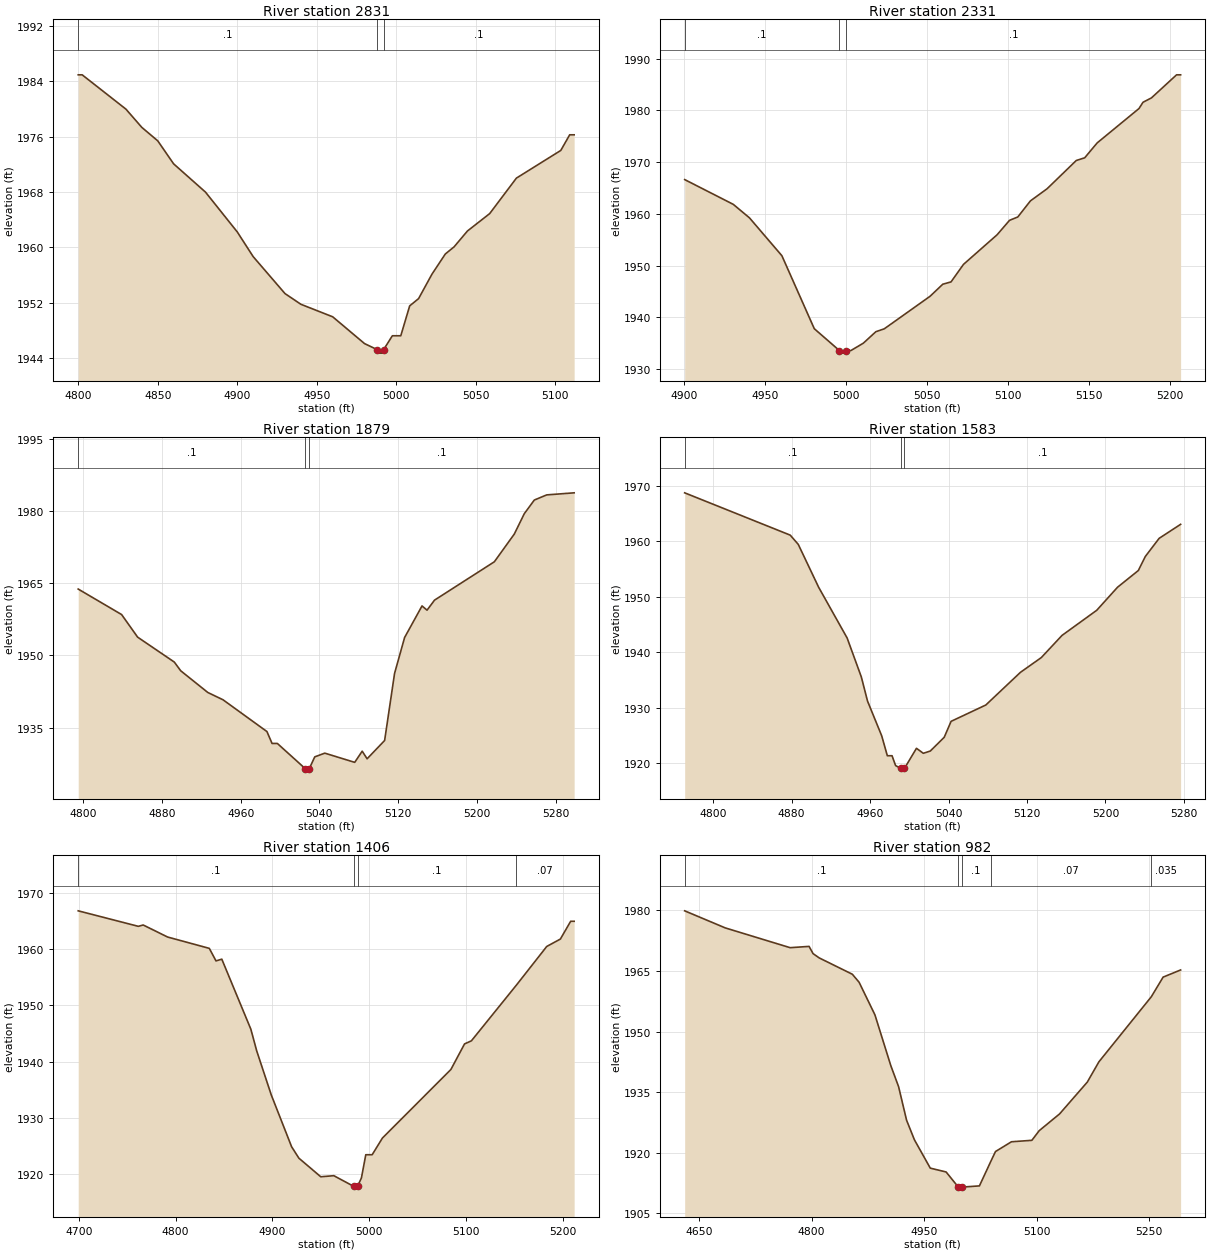
Type RM Length L Ch R = 1,2831,500,500,500
BEGIN DESCRIPTION:
Stream0169 6.0
END DESCRIPTION:
XS GIS Cut Line= 3
      1818025.00     13935075.00      1818025.00     13934875.00
      1818075.00     13934775.01
#Sta/Elev= 30
  4800.0 1984.95  4802.5 1984.95  4830.0 1979.99  4840.0 1977.35  4850.0 1975.41
  4860.0 1972.08  4880.0 1968.00  4900.0 1962.24  4910.0 1958.67  4930.0 1953.33
  4940.0 1951.78  4960.0 1949.97  4980.0 1946.10  4988.0 1945.22  4988.3 1944.72
  4991.8 1944.72  4992.0 1945.22  4997.5 1947.23  5002.8 1947.23  5008.4 1951.55
  5014.0 1952.60  5022.4 1956.13  5030.8 1959.05  5036.3 1960.08  5044.7 1962.37
  5058.7 1964.89  5075.5 1970.02  5103.4 1974.02  5109.0 1976.28  5111.8 1976.28
#Mann=3,-1,0
  4800.0     0.1       0  4988.0    0.05       0  4992.0     0.1       0
Bank Sta=4988,4992
Exp/Cntr=0.3,0.1

Type RM Length L Ch R = 1,2331,452,452,452
BEGIN DESCRIPTION:
Stream0169 5.0
END DESCRIPTION:
XS GIS Cut Line= 3
      1818525.00     13934974.98      1818525.00     13934875.00
      1818475.01     13934675.04
#Sta/Elev= 30
  4900.4 1966.64  4930.4 1961.85  4940.4 1959.24  4960.4 1951.92  4980.4 1937.81
  4995.9 1933.59  4996.1 1933.09  4999.6 1933.09  4999.9 1933.59  5003.0 1933.59
  5010.7 1935.02  5018.4 1937.23  5023.6 1937.79  5051.9 1944.09  5059.7 1946.41
  5064.8 1946.86  5072.5 1950.25  5093.2 1955.96  5100.9 1958.76  5106.0 1959.41
  5113.8 1962.52  5124.1 1964.87  5142.1 1970.33  5147.3 1970.85  5155.0 1973.73
  5180.8 1980.37  5183.3 1981.59  5188.5 1982.43  5204.0 1986.89  5206.5 1986.89
#Mann=3,-1,0
  4900.4     0.1       0  4995.9    0.05       0  4999.9     0.1       0
Bank Sta=4995.9,4999.9
Exp/Cntr=0.3,0.1

Type RM Length L Ch R = 1,1879,296,296,296
BEGIN DESCRIPTION:
Stream0169 4.0
END DESCRIPTION:
XS GIS Cut Line= 3
      1818830.21     13935100.96      1818925.00     13934925.00
      1818875.00     13934625.01
#Sta/Elev= 30
  4794.9 1963.78  4839.0 1958.49  4855.3 1953.80  4892.5 1948.64  4899.1 1946.82
  4926.6 1942.32  4942.1 1940.80  4986.7 1934.21  4991.9 1931.74  4997.3 1931.74
  5025.7 1926.50  5026.0 1926.00  5029.7 1926.50  5035.3 1928.96  5045.5 1929.73
  5075.9 1927.82  5083.5 1930.14  5088.5 1928.56  5106.3 1932.36  5116.4 1946.28
  5126.6 1953.73  5144.3 1960.28  5149.4 1959.40  5157.0 1961.48  5217.8 1969.44
  5238.1 1975.20  5248.2 1979.41  5258.4 1982.25  5271.0 1983.32  5298.9 1983.75
#Mann=3,-1,0
  4794.9     0.1       0  5025.7    0.05       0  5029.7     0.1       0
Bank Sta=5025.7,5029.7
Exp/Cntr=0.3,0.1

Type RM Length L Ch R = 1,1583,177,177,177
BEGIN DESCRIPTION:
Stream0169 3.1
END DESCRIPTION:
XS GIS Cut Line= 3
      1819323.31     13935098.33      1819194.13     13934930.95
      1818985.09     13934723.99
#Sta/Elev= 30
  4771.0 1968.77  4878.6 1961.13  4886.8 1959.46  4907.6 1951.71  4936.6 1942.56
  4951.1 1935.52  4957.4 1931.17  4971.9 1924.87  4977.6 1921.29  4982.4 1921.29
  4986.0 1919.52  4991.1 1919.01  4991.4 1918.51  4994.9 1918.51  4995.1 1919.01
  5007.3 1922.63  5014.3 1921.73  5021.4 1922.14  5035.6 1924.62  5042.6 1927.50
  5078.0 1930.45  5113.3 1936.35  5134.6 1939.02  5155.7 1943.02  5191.1 1947.56
  5212.3 1951.72  5233.5 1954.74  5240.6 1957.27  5254.7 1960.55  5276.6 1963.08
#Mann=3,-1,0
  4771.0     0.1       0  4991.1    0.05       0  4995.1     0.1       0
Bank Sta=4991.1,4995.1
Exp/Cntr=0.3,0.1

Type RM Length L Ch R = 1,1406,424,424,424
BEGIN DESCRIPTION:
Stream0169 3.0
END DESCRIPTION:
XS GIS Cut Line= 4
      1819373.60     13935047.19      1819366.32     13934911.98
      1819275.00     13934775.00      1819124.98     13934624.98
#Sta/Elev= 30
  4699.5 1966.83  4761.6 1964.07  4766.6 1964.31  4791.8 1962.17  4834.9 1960.15
  4841.8 1957.92  4847.8 1958.23  4877.8 1945.77  4883.9 1941.88  4898.9 1934.07
  4919.9 1924.85  4927.4 1922.82  4950.0 1919.51  4963.5 1919.70  4984.0 1917.81
  4984.3 1917.31  4987.8 1917.31  4988.0 1917.81  4992.0 1919.30  4996.5 1923.43
  5003.1 1923.43  5013.7 1926.40  5084.4 1938.60  5098.5 1943.15  5105.6 1943.70
  5152.1 1953.62  5183.4 1960.49  5197.5 1961.81  5208.1 1964.97  5211.7 1964.97
#Mann=4,-1,0
  4699.5     0.1       0  4984.0    0.05       0  4988.0     0.1       0
  5152.1    0.07       0
Bank Sta=4984,4988
Exp/Cntr=0.3,0.1

Type RM Length L Ch R = 1,982,453,453,453
BEGIN DESCRIPTION:
Stream0169 2.0
END DESCRIPTION:
XS GIS Cut Line= 4
      1819873.61     13934597.52      1819667.16     13934522.39
      1819525.00     13934475.00      1819275.00     13934325.00
#Sta/Elev= 30
  4630.8 1979.91  4684.9 1975.68  4771.4 1970.78  4796.6 1971.10  4802.0 1969.30
  4810.2 1968.24  4854.3 1964.20  4863.3 1962.22  4884.4 1954.15  4905.5 1941.61
  4916.0 1936.32  4926.6 1928.04  4937.1 1923.17  4958.2 1916.17  4979.3 1915.22
  4995.6 1911.47  4995.9 1910.97  4999.9 1911.47  5023.7 1911.77  5038.9 1917.85
  5045.1 1920.28  5066.4 1922.70  5093.6 1923.06  5103.4 1925.45  5130.6 1929.61
  5167.5 1937.48  5183.0 1942.51  5252.9 1958.64  5268.6 1963.49  5291.9 1965.26
#Mann=5,-1,0
  4630.8     0.1       0  4995.6    0.05       0  4999.9     0.1       0
  5038.9    0.07       0  5252.9   0.035       0
Bank Sta=4995.6,4999.9
Exp/Cntr=0.3,0.1

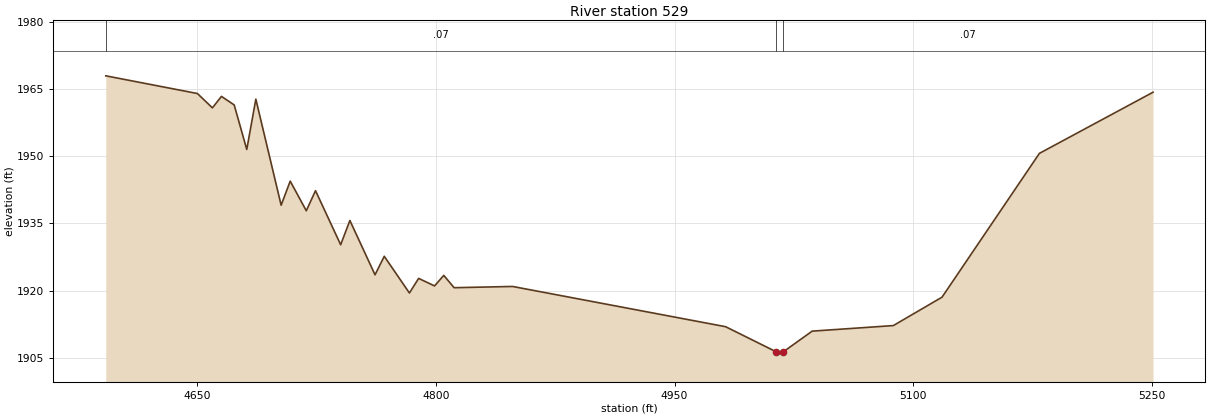
Type RM Length L Ch R = 1,529,0,0,0
BEGIN DESCRIPTION:
Stream0169 1.0
END DESCRIPTION:
XS GIS Cut Line= 3
      1819875.02     13934425.04      1819675.00     13934075.00
      1819425.01     13934025.00
#Sta/Elev= 30
  4592.6 1967.95  4650.2 1964.00  4659.6 1960.80  4665.3 1963.36  4673.3 1961.45
  4681.2 1951.52  4686.9 1962.75  4702.8 1939.08  4708.5 1944.45  4718.6 1937.84
  4724.4 1942.32  4740.2 1930.26  4746.0 1935.67  4761.8 1923.55  4767.6 1927.68
  4783.4 1919.49  4789.2 1922.75  4799.2 1921.07  4805.0 1923.42  4811.5 1920.67
  4848.2 1920.95  4982.1 1911.97  5014.0 1906.35  5014.3 1905.85  5018.3 1906.35
  5036.5 1910.98  5087.5 1912.22  5118.1 1918.56  5179.3 1950.65  5250.7 1964.29
#Mann=3,-1,0
  4592.6    0.07       0  5014.0    0.05       0  5018.3    0.07       0
Bank Sta=5014,5018.3
Exp/Cntr=0.3,0.1

Chan Stop Cuts=-1