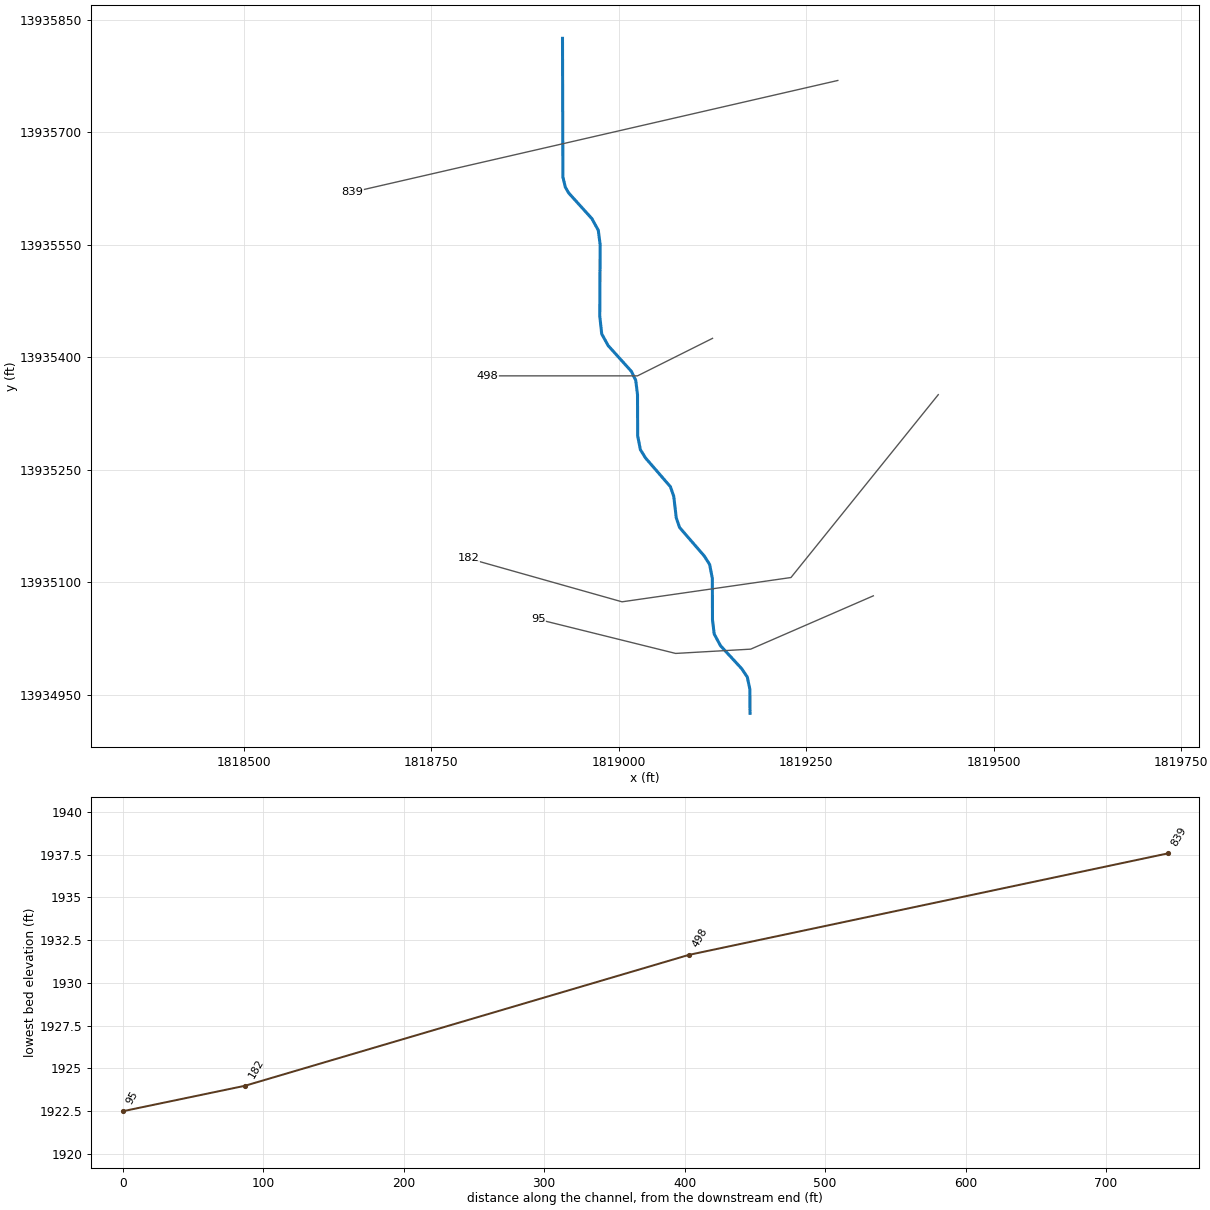
--- Stream0170.prj (project) ---

Proj Title=Stream0170 Base Level Engineering
Current Plan=p01
Default Exp/Contr=0.3,0.1
English Units
Geom File=g01
Flow File=f01
Plan File=p01
BEGIN DESCRIPTION:
Stream0170
END DESCRIPTION:

--- Stream0170.p01 (plan) ---

Plan Title=Multiple Run
Short Identifier=Multiple
Geom File=g01
Flow File=f01
Subcritical Flow
K Sum by GR= 0
Std Step Tol= 0.01
Critical Tol= 0.01
Num of Std Step Trials= 20
Max Error Tol= 0.3
Flow Tol Ratio= 0.001
Split Flow NTrial= 30
Split Flow Tol= 0.02
Split Flow Ratio= 0.02
Log Output Level= 0
Friction Slope Method= 1
Unsteady Friction Slope Method= 2
Unsteady Bridges Friction Slope Method= 1
Parabolic Critical Depth
Global Vel Dist=  1 , 1 , 1
Global Log Level= 0
CheckData=True
Encroach Param= -1, 0, 0, 0
BEGIN DESCRIPTION:
Multiple Run
END DESCRIPTION:

--- Stream0170.f01 (steady flow) ---

Flow Title=Multiple
Number of Profiles=7
Profile Names=10-year,25-year,50-year,1pct_min,100-year,1pct_plu,500-year
River Rch & RM= Stream0170,Reach-1,839
     744    1260    1747    1174    2343    4676    4160
Boundary for River Rch & Prof#=Stream0170,Reach-1,1
Up Type=0
Dn Type=3
Dn Slope=0.005
Boundary for River Rch & Prof#=Stream0170,Reach-1,2
Up Type=0
Dn Type=3
Dn Slope=0.005
Boundary for River Rch & Prof#=Stream0170,Reach-1,3
Up Type=0
Dn Type=3
Dn Slope=0.005
Boundary for River Rch & Prof#=Stream0170,Reach-1,4
Up Type=0
Dn Type=3
Dn Slope=0.005
Boundary for River Rch & Prof#=Stream0170,Reach-1,5
Up Type=0
Dn Type=3
Dn Slope=0.005
Boundary for River Rch & Prof#=Stream0170,Reach-1,6
Up Type=0
Dn Type=3
Dn Slope=0.005
Boundary for River Rch & Prof#=Stream0170,Reach-1,7
Up Type=0
Dn Type=3
Dn Slope=0.005

--- Stream0170.g01 (geometry) ---

Geom Title=Existing Conditions

River Reach=Stream0170,Reach-1
Reach XY= 30
      1818925.00     13935825.00      1818925.51     13935640.21
      1818928.78     13935626.56      1818933.14     13935618.94
      1818964.14     13935584.65      1818972.73     13935569.06
      1818975.18     13935550.07      1818974.68     13935454.87
      1818977.27     13935430.94      1818985.85     13935415.35
      1819016.81     13935381.03      1819022.64     13935369.02
      1819025.00     13935350.00      1819025.23     13935295.09
      1819028.83     13935276.58      1819035.84     13935265.35
      1819068.89     13935227.18      1819073.33     13935214.31
      1819076.67     13935185.69      1819081.11     13935172.82
      1819114.16     13935134.65      1819121.18     13935123.42
      1819124.78     13935104.91      1819124.97     13935049.99
      1819127.23     13935030.92      1819135.61     13935015.25
      1819163.95     13934984.56      1819171.36     13934973.49
      1819174.88     13934956.80      1819175.00     13934925.00

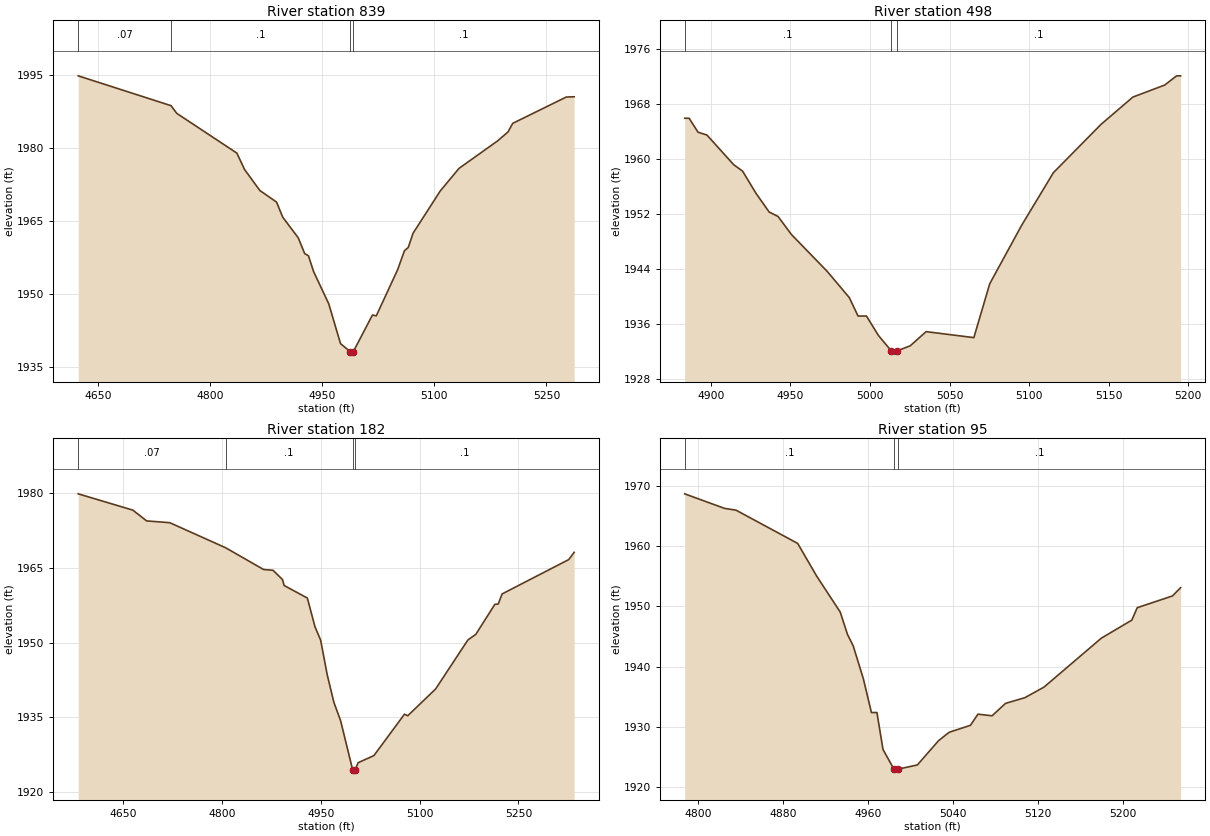
Type RM Length L Ch R = 1,839,341,341,341
BEGIN DESCRIPTION:
Stream01700 2.0
END DESCRIPTION:
XS GIS Cut Line= 2
      1819292.05     13935768.82      1818644.76     13935619.89
#Sta/Elev= 30
  4623.0 1994.83  4747.3 1988.69  4755.0 1987.11  4835.5 1978.93  4845.8 1975.56
  4866.2 1971.25  4888.6 1968.86  4897.0 1965.73  4917.6 1961.53  4926.3 1958.27
  4931.4 1957.80  4938.1 1954.62  4958.6 1947.91  4974.3 1939.74  4987.4 1938.08
  4987.6 1937.58  4991.4 1938.08  5017.1 1945.63  5022.2 1945.45  5050.9 1954.98
  5059.9 1958.85  5065.0 1959.52  5071.5 1962.46  5107.9 1971.15  5133.0 1975.79
  5184.3 1981.40  5198.6 1983.28  5204.9 1985.05  5276.7 1990.47  5287.2 1990.52
#Mann=4,-1,0
  4623.0    0.07       0  4747.3     0.1       0  4987.4    0.05       0
  4991.4     0.1       0
Bank Sta=4987.4,4991.4
Exp/Cntr=0.3,0.1

Type RM Length L Ch R = 1,498,316,316,316
BEGIN DESCRIPTION:
Stream0170 1.0
END DESCRIPTION:
XS GIS Cut Line= 3
      1819125.04     13935425.02      1819025.00     13935375.00
      1818825.04     13935375.00
#Sta/Elev= 30
  4883.5 1965.94  4886.3 1965.94  4891.9 1963.91  4897.5 1963.50  4914.3 1959.19
  4919.9 1958.25  4928.3 1955.04  4936.6 1952.31  4942.2 1951.66  4950.6 1949.04
  4973.0 1943.70  4987.0 1939.86  4992.5 1937.18  4997.8 1937.18  5005.3 1934.36
  5013.3 1932.14  5013.6 1931.64  5017.1 1931.64  5017.3 1932.14  5025.3 1932.85
  5035.3 1934.91  5065.3 1934.04  5075.3 1941.88  5095.3 1950.35  5115.3 1958.02
  5145.3 1965.06  5165.3 1969.02  5185.3 1970.77  5192.8 1972.11  5195.3 1972.11
#Mann=3,-1,0
  4883.5     0.1       0  5013.3    0.05       0  5017.3     0.1       0
Bank Sta=5013.3,5017.3
Exp/Cntr=0.3,0.1

Type RM Length L Ch R = 1,182,87,87,87
BEGIN DESCRIPTION:
Stream0170 0.0
END DESCRIPTION:
XS GIS Cut Line= 4
      1819426.01     13935349.93      1819229.60     13935106.13
      1819004.35     13935073.74      1818799.70     13935131.55
#Sta/Elev= 30
  4581.4 1979.89  4664.5 1976.61  4685.3 1974.45  4720.5 1974.09  4805.4 1969.05
  4862.9 1964.69  4877.3 1964.53  4891.7 1962.67  4894.2 1961.47  4929.4 1958.96
  4941.1 1953.16  4949.6 1950.52  4959.7 1943.49  4969.8 1937.98  4979.9 1934.34
  4998.2 1924.48  4998.4 1923.98  5002.2 1924.48  5006.5 1925.87  5030.5 1927.30
  5077.0 1935.62  5082.0 1935.31  5124.3 1940.69  5173.3 1950.53  5185.4 1951.67
  5214.2 1957.68  5219.4 1957.76  5225.3 1959.78  5326.5 1966.68  5334.7 1968.14
#Mann=4,-1,0
  4581.4    0.07       0  4805.4     0.1       0  4998.2    0.05       0
  5002.2     0.1       0
Bank Sta=4998.2,5002.2
Exp/Cntr=0.3,0.1

Type RM Length L Ch R = 1,95,0,0,0
BEGIN DESCRIPTION:
Stream0170 0.1
END DESCRIPTION:
XS GIS Cut Line= 4
      1819339.42     13935081.72      1819175.94     13935010.64
      1819075.83     13935004.92      1818892.52     13935050.38
#Sta/Elev= 30
  4787.0 1968.63  4824.5 1966.22  4835.4 1965.92  4893.5 1960.41  4911.5 1954.96
  4933.6 1949.03  4940.4 1945.34  4945.9 1943.39  4955.4 1937.96  4963.0 1932.37
  4968.2 1932.37  4973.9 1926.25  4984.2 1922.99  4984.5 1922.49  4988.0 1922.49
  4988.2 1922.99  5006.3 1923.68  5026.3 1927.71  5036.3 1929.10  5056.3 1930.25
  5063.4 1932.10  5076.7 1931.83  5089.4 1933.89  5107.6 1934.83  5125.6 1936.58
  5179.7 1944.70  5208.4 1947.69  5213.5 1949.75  5246.7 1951.70  5254.4 1953.07
#Mann=3,-1,0
  4787.0     0.1       0  4984.2    0.05       0  4988.2     0.1       0
Bank Sta=4984.2,4988.2
Exp/Cntr=0.3,0.1

Chan Stop Cuts=-1