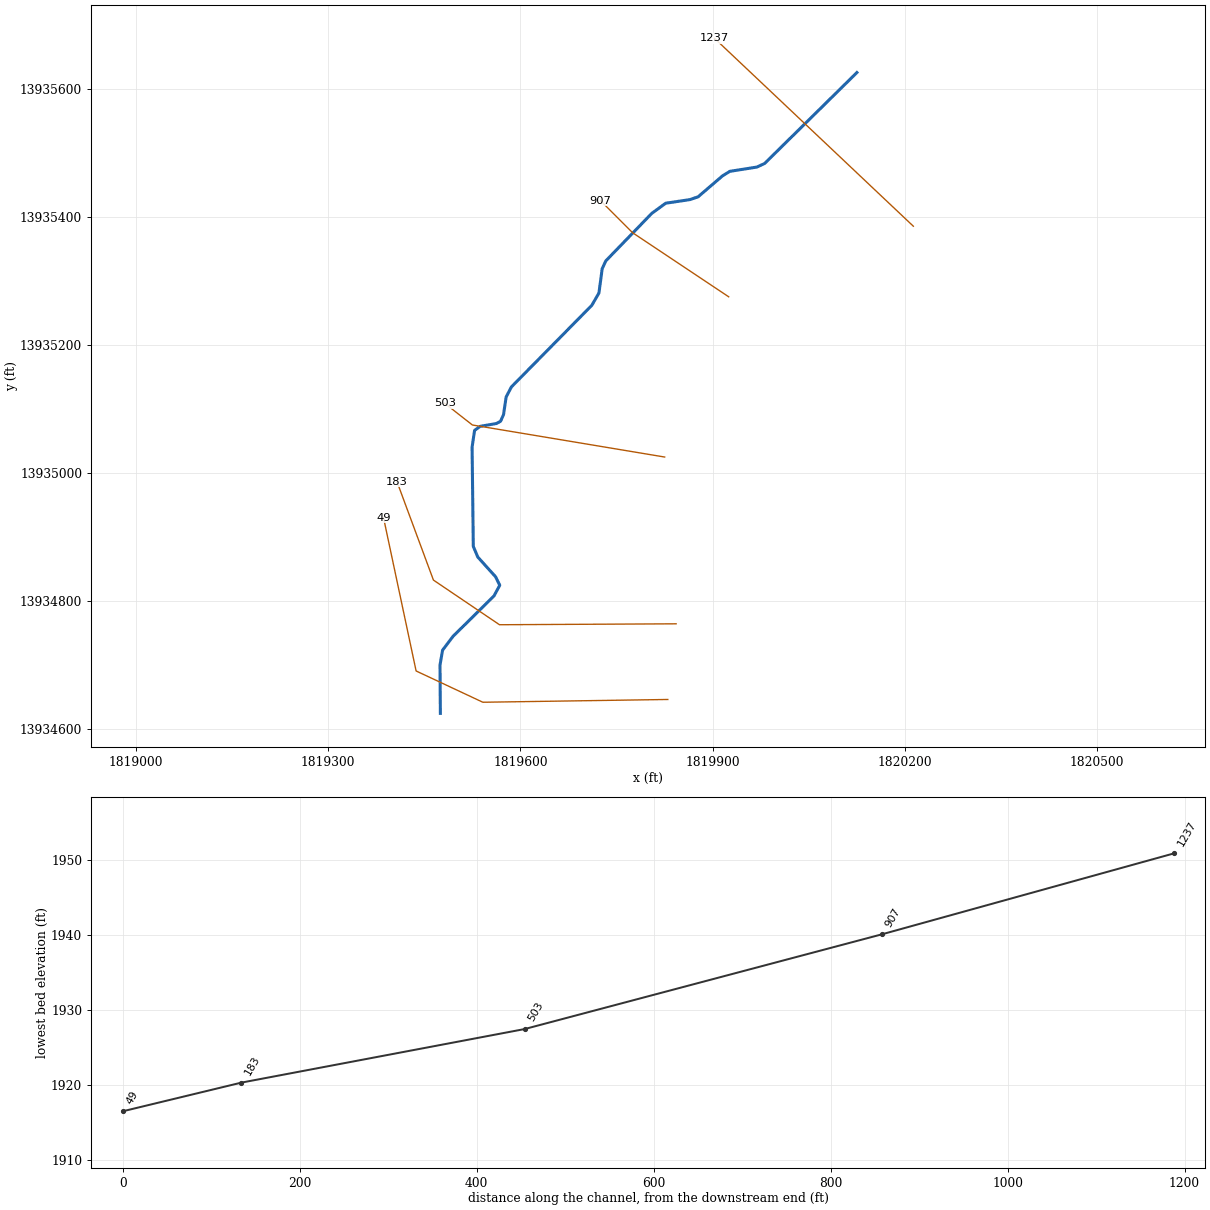
--- Stream0171.prj (project) ---

Proj Title=Stream0171 Base Level Engineering
Current Plan=p01
Default Exp/Contr=0.3,0.1
English Units
Geom File=g01
Flow File=f01
Plan File=p01
BEGIN DESCRIPTION:
Stream0171
END DESCRIPTION:

--- Stream0171.p01 (plan) ---

Plan Title=Multiple Run
Short Identifier=Multiple
Geom File=g01
Flow File=f01
Subcritical Flow
K Sum by GR= 0
Std Step Tol= 0.01
Critical Tol= 0.01
Num of Std Step Trials= 20
Max Error Tol= 0.3
Flow Tol Ratio= 0.001
Split Flow NTrial= 30
Split Flow Tol= 0.02
Split Flow Ratio= 0.02
Log Output Level= 0
Friction Slope Method= 1
Unsteady Friction Slope Method= 2
Unsteady Bridges Friction Slope Method= 1
Parabolic Critical Depth
Global Vel Dist=  1 , 1 , 1
Global Log Level= 0
CheckData=True
Encroach Param= -1, 0, 0, 0
BEGIN DESCRIPTION:
Multiple Run
END DESCRIPTION:

--- Stream0171.f01 (steady flow) ---

Flow Title=Multiple
Number of Profiles=7
Profile Names=10-year,25-year,50-year,1pct_min,100-year,1pct_plu,500-year
River Rch & RM= Stream0171,Reach-1,1237
     496     820    1119     743    1483    2958    2562
Boundary for River Rch & Prof#=Stream0171,Reach-1,1
Up Type=0
Dn Type=3
Dn Slope=0.005
Boundary for River Rch & Prof#=Stream0171,Reach-1,2
Up Type=0
Dn Type=3
Dn Slope=0.005
Boundary for River Rch & Prof#=Stream0171,Reach-1,3
Up Type=0
Dn Type=3
Dn Slope=0.005
Boundary for River Rch & Prof#=Stream0171,Reach-1,4
Up Type=0
Dn Type=3
Dn Slope=0.005
Boundary for River Rch & Prof#=Stream0171,Reach-1,5
Up Type=0
Dn Type=3
Dn Slope=0.005
Boundary for River Rch & Prof#=Stream0171,Reach-1,6
Up Type=0
Dn Type=3
Dn Slope=0.005
Boundary for River Rch & Prof#=Stream0171,Reach-1,7
Up Type=0
Dn Type=3
Dn Slope=0.005

--- Stream0171.g01 (geometry) ---

Geom Title=Existing Conditions

River Reach=Stream0171,Reach-1
Reach XY= 30
      1820125.00     13935625.00      1819981.06     13935483.14
      1819968.97     13935477.50      1819926.73     13935470.81
      1819915.45     13935463.90      1819877.19     13935431.10
      1819864.29     13935426.70      1819826.62     13935421.06
      1819804.87     13935405.23      1819733.15     13935331.07
      1819727.53     13935318.96      1819722.46     13935281.05
      1819711.37     13935261.79      1819585.85     13935134.43
      1819577.60     13935118.61      1819573.55     13935091.16
      1819568.94     13935080.80      1819562.47     13935077.33
      1819537.07     13935072.86      1819528.40     13935066.56
      1819524.49     13935040.49      1819526.39     13934885.44
      1819533.47     13934868.81      1819561.17     13934838.16
      1819567.67     13934824.90      1819558.68     13934808.31
      1819494.71     13934745.16      1819478.41     13934723.60
      1819474.41     13934700.25      1819475.00     13934625.00

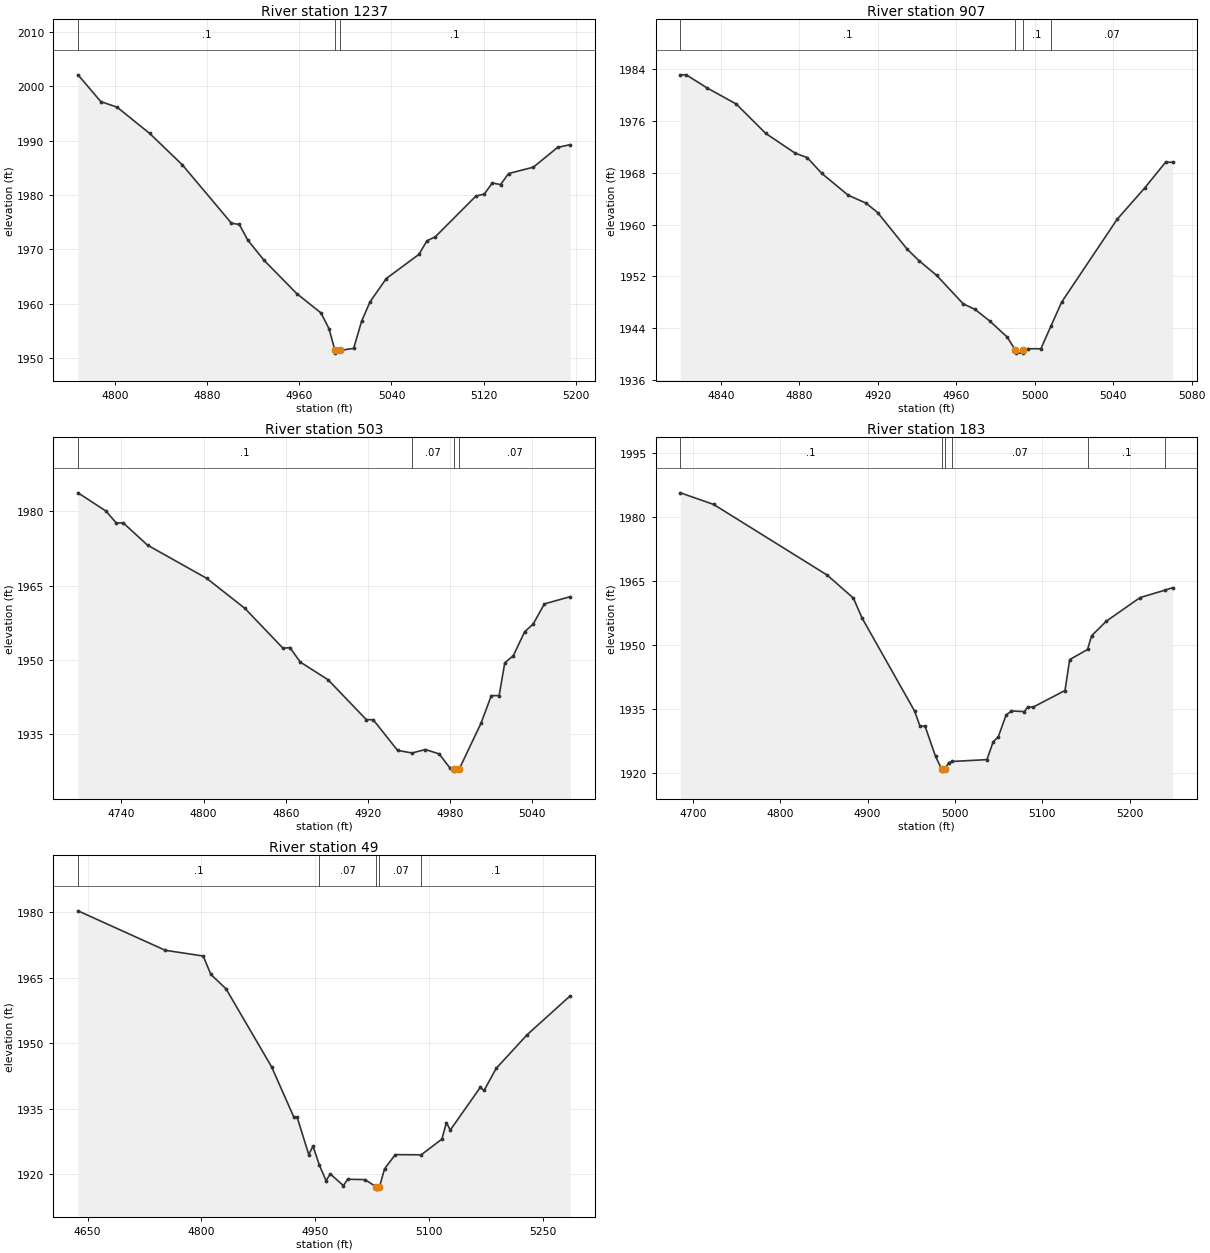
Type RM Length L Ch R = 1,1237,330,330,330
BEGIN DESCRIPTION:
Stream0171 3.0
END DESCRIPTION:
XS GIS Cut Line= 2
      1820213.03     13935385.20      1819902.85     13935678.37
#Sta/Elev= 30
  4768.2 2002.08  4787.9 1997.17  4802.1 1996.13  4830.4 1991.30  4858.7 1985.53
  4901.2 1974.82  4908.1 1974.58  4915.4 1971.70  4929.5 1968.00  4957.8 1961.89
  4978.9 1958.32  4985.8 1955.44  4991.0 1951.44  4991.3 1950.94  4995.0 1951.44
  5007.2 1951.81  5014.1 1956.82  5021.4 1960.37  5035.5 1964.65  5063.8 1969.09
  5070.7 1971.57  5078.0 1972.32  5113.2 1979.80  5120.5 1980.17  5127.4 1982.21
  5134.6 1981.91  5141.5 1983.94  5163.0 1985.11  5184.0 1988.74  5195.0 1989.25
#Mann=3,-1,0
  4768.2     0.1       0  4991.0    0.05       0  4995.0     0.1       0
Bank Sta=4991,4995
Exp/Cntr=0.3,0.1

Type RM Length L Ch R = 1,907,404,404,404
BEGIN DESCRIPTION:
Stream0171 2.0
END DESCRIPTION:
XS GIS Cut Line= 3
      1819924.97     13935275.02      1819775.00     13935375.00
      1819724.96     13935425.04
#Sta/Elev= 30
  4819.3 1983.17  4822.3 1983.17  4832.8 1981.16  4847.8 1978.65  4862.8 1974.12
  4877.9 1971.04  4883.9 1970.39  4891.4 1967.93  4904.9 1964.55  4913.9 1963.35
  4919.9 1961.87  4934.9 1956.23  4940.9 1954.46  4950.0 1952.16  4963.5 1947.77
  4969.5 1946.92  4977.0 1945.12  4986.0 1942.62  4990.0 1940.65  4990.3 1940.15
  4993.8 1940.15  4994.0 1940.65  4996.5 1940.83  5003.1 1940.83  5008.2 1944.30
  5013.7 1948.04  5042.0 1960.84  5056.1 1965.70  5066.7 1969.66  5070.3 1969.66
#Mann=4,-1,0
  4819.3     0.1       0  4990.0    0.05       0  4994.0     0.1       0
  5008.2    0.07       0
Bank Sta=4990,4994
Exp/Cntr=0.3,0.1

Type RM Length L Ch R = 1,503,320,320,320
BEGIN DESCRIPTION:
Stream0171 1.0
END DESCRIPTION:
XS GIS Cut Line= 3
      1819825.02     13935025.00      1819525.00     13935075.00
      1819481.65     13935108.92
#Sta/Elev= 30
  4708.4 1983.75  4728.7 1980.08  4736.3 1977.67  4741.4 1977.67  4759.1 1973.18
  4802.2 1966.49  4830.1 1960.42  4858.0 1952.34  4863.0 1952.47  4870.6 1949.55
  4890.9 1945.97  4918.8 1937.91  4923.8 1937.90  4941.6 1931.70  4952.2 1931.18
  4961.9 1931.88  4972.0 1930.98  4979.6 1928.21  4982.7 1928.01  4982.9 1927.51
  4986.7 1928.01  5002.4 1937.14  5010.0 1942.77  5015.7 1942.77  5019.8 1949.38
  5026.1 1950.87  5034.3 1955.66  5040.6 1957.26  5048.7 1961.30  5067.6 1962.77
#Mann=4,-1,0
  4708.4     0.1       0  4952.2    0.07       0  4982.7    0.05       0
  4986.7    0.07       0
Bank Sta=4982.7,4986.7
Exp/Cntr=0.3,0.1

Type RM Length L Ch R = 1,183,134,134,134
BEGIN DESCRIPTION:
Stream0171 0.0
END DESCRIPTION:
XS GIS Cut Line= 4
      1819842.97     13934764.76      1819567.26     13934763.32
      1819464.16     13934833.01      1819407.43     13934986.18
#Sta/Elev= 30
  4685.8 1985.69  4723.8 1982.97  4853.8 1966.39  4883.8 1960.99  4893.8 1956.29
  4953.8 1934.51  4960.1 1930.92  4965.9 1930.92  4977.9 1923.81  4984.8 1920.87
  4985.1 1920.37  4988.8 1920.87  4992.9 1922.38  4997.1 1922.64  5036.7 1923.07
  5043.8 1927.22  5049.8 1928.48  5058.7 1933.56  5064.8 1934.49  5079.7 1934.34
  5083.3 1935.41  5089.7 1935.41  5126.1 1939.29  5131.4 1946.54  5151.9 1948.93
  5156.5 1952.14  5173.4 1955.57  5211.9 1961.09  5240.9 1962.87  5249.3 1963.43
#Mann=6,-1,0
  4685.8     0.1       0  4984.8    0.05       0  4988.8     0.1       0
  4997.1    0.07       0  5151.9     0.1       0  5240.9    0.07       0
Bank Sta=4984.8,4988.8
Exp/Cntr=0.3,0.1

Type RM Length L Ch R = 1,49,0,0,0
BEGIN DESCRIPTION:
Stream0171 0.1
END DESCRIPTION:
XS GIS Cut Line= 4
      1819829.92     13934646.70      1819541.31     13934642.36
      1819437.14     13934691.19      1819386.26     13934930.45
#Sta/Elev= 30
  4637.4 1980.29  4752.3 1971.25  4802.3 1969.94  4812.3 1965.74  4832.3 1962.43
  4892.3 1944.58  4921.7 1933.02  4926.0 1933.02  4941.3 1924.46  4946.8 1926.40
  4955.4 1922.01  4964.1 1918.48  4969.6 1920.04  4986.9 1917.35  4992.5 1918.81
  5015.3 1918.73  5030.4 1917.05  5030.7 1916.55  5034.4 1917.05  5041.1 1921.19
  5055.2 1924.45  5089.4 1924.41  5116.6 1928.00  5122.6 1931.79  5127.7 1930.08
  5167.1 1939.83  5172.2 1939.14  5188.1 1944.20  5229.0 1951.93  5285.7 1960.83
#Mann=5,-1,0
  4637.4     0.1       0  4955.4    0.07       0  5030.4    0.05       0
  5034.4    0.07       0  5089.4     0.1       0
Bank Sta=5030.4,5034.4
Exp/Cntr=0.3,0.1

Chan Stop Cuts=-1