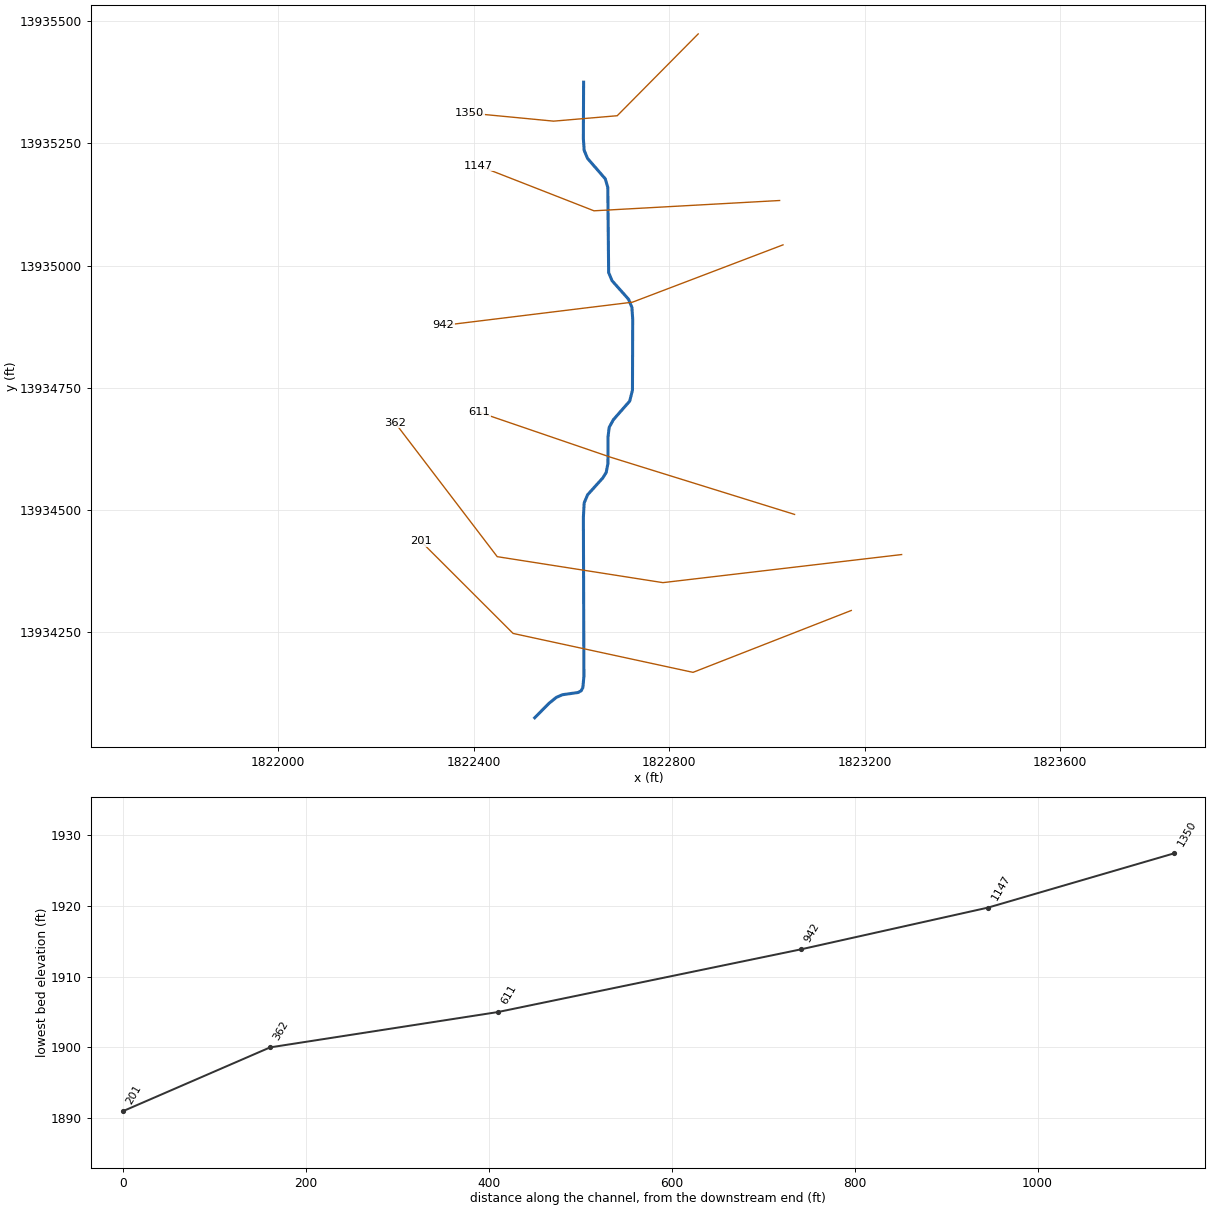
--- Stream0172.prj (project) ---

Proj Title=Stream0172 Base Level Engineering
Current Plan=p01
Default Exp/Contr=0.3,0.1
English Units
Geom File=g01
Flow File=f01
Plan File=p01
BEGIN DESCRIPTION:
Stream0172
END DESCRIPTION:

--- Stream0172.p01 (plan) ---

Plan Title=Multiple Run
Short Identifier=Multiple
Geom File=g01
Flow File=f01
Subcritical Flow
K Sum by GR= 0
Std Step Tol= 0.01
Critical Tol= 0.01
Num of Std Step Trials= 20
Max Error Tol= 0.3
Flow Tol Ratio= 0.001
Split Flow NTrial= 30
Split Flow Tol= 0.02
Split Flow Ratio= 0.02
Log Output Level= 0
Friction Slope Method= 1
Unsteady Friction Slope Method= 2
Unsteady Bridges Friction Slope Method= 1
Parabolic Critical Depth
Global Vel Dist=  1 , 1 , 1
Global Log Level= 0
CheckData=True
Encroach Param= -1, 0, 0, 0
BEGIN DESCRIPTION:
Multiple Run
END DESCRIPTION:

--- Stream0172.f01 (steady flow) ---

Flow Title=Multiple
Number of Profiles=7
Profile Names=10-year,25-year,50-year,1pct_min,100-year,1pct_plu,500-year
River Rch & RM= Stream0172,Reach-1,1350
     496     822    1124     748    1492    2977    2589
Boundary for River Rch & Prof#=Stream0172,Reach-1,1
Up Type=0
Dn Type=3
Dn Slope=0.005
Boundary for River Rch & Prof#=Stream0172,Reach-1,2
Up Type=0
Dn Type=3
Dn Slope=0.005
Boundary for River Rch & Prof#=Stream0172,Reach-1,3
Up Type=0
Dn Type=3
Dn Slope=0.005
Boundary for River Rch & Prof#=Stream0172,Reach-1,4
Up Type=0
Dn Type=3
Dn Slope=0.005
Boundary for River Rch & Prof#=Stream0172,Reach-1,5
Up Type=0
Dn Type=3
Dn Slope=0.005
Boundary for River Rch & Prof#=Stream0172,Reach-1,6
Up Type=0
Dn Type=3
Dn Slope=0.005
Boundary for River Rch & Prof#=Stream0172,Reach-1,7
Up Type=0
Dn Type=3
Dn Slope=0.005

--- Stream0172.g01 (geometry) ---

Geom Title=Existing Conditions

River Reach=Stream0172,Reach-1
Reach XY= 30
      1822625.00     13935375.00      1822624.49     13935259.79
      1822626.17     13935235.48      1822633.13     13935218.94
      1822669.26     13935177.34      1822674.48     13935159.78
      1822676.22     13934985.51      1822683.14     13934968.94
      1822716.86     13934931.06      1822723.78     13934914.49
      1822725.43     13934890.18      1822724.93     13934745.03
      1822719.26     13934722.67      1822685.89     13934684.63
      1822677.36     13934669.02      1822675.00     13934650.00
      1822674.76     13934595.10      1822671.14     13934576.60
      1822664.11     13934565.37      1822633.14     13934531.06
      1822626.22     13934514.50      1822624.55     13934485.19
      1822625.63     13934159.44      1822623.46     13934136.71
      1822619.98     13934130.23      1822613.54     13934126.70
      1822581.73     13934122.16      1822569.37     13934116.85
      1822554.37     13934104.73      1822525.00     13934075.00

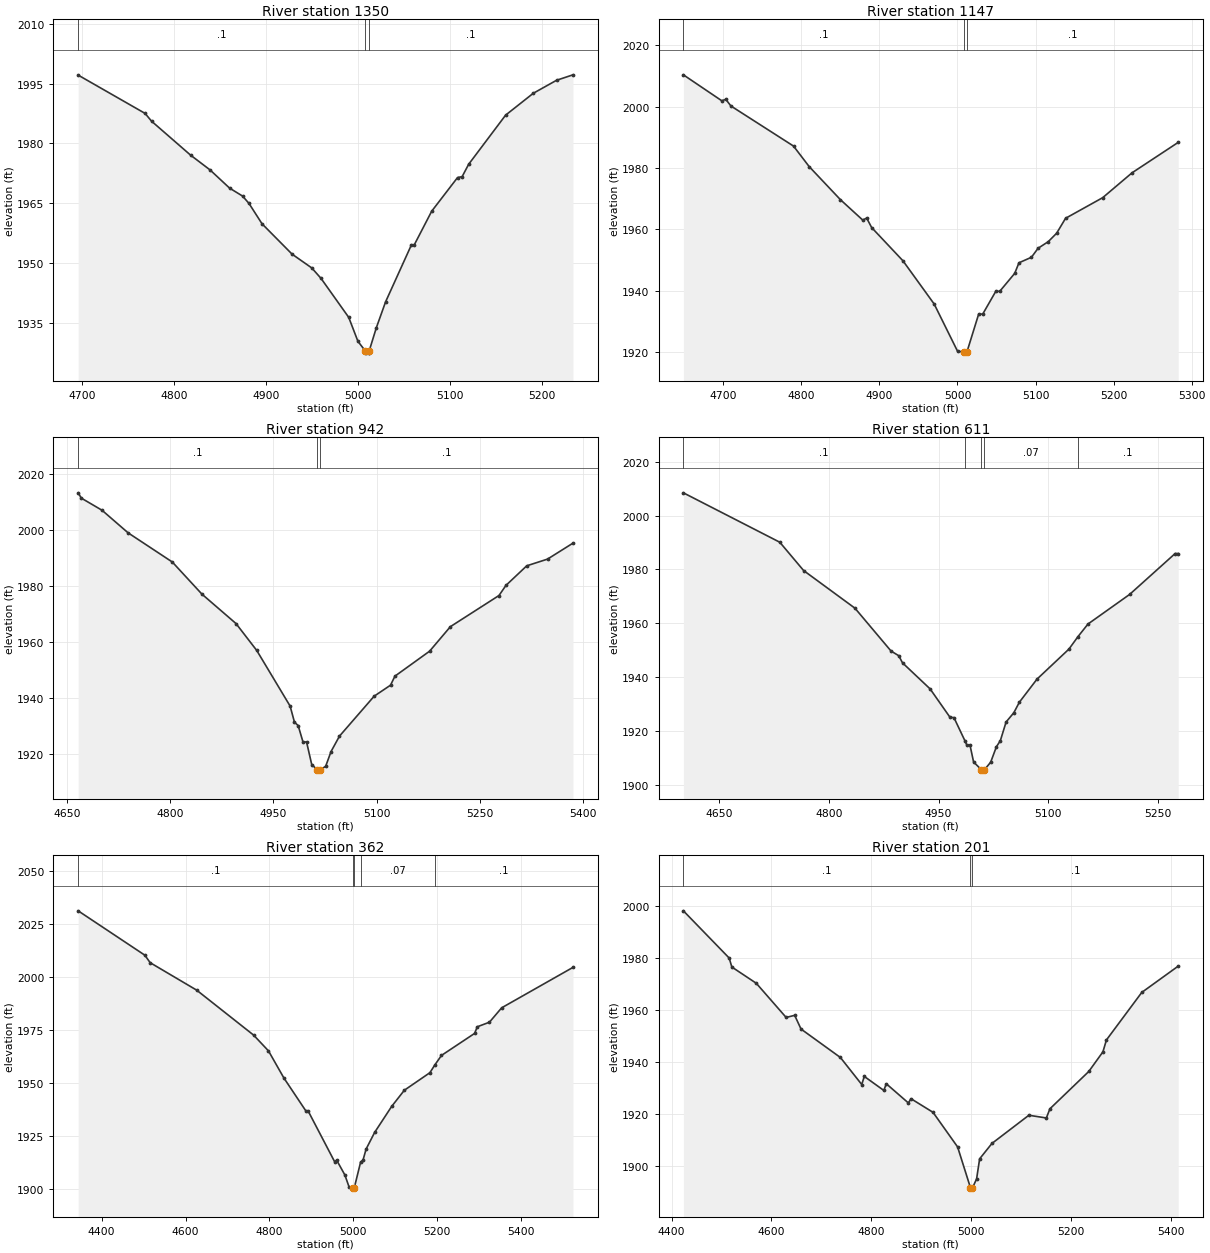
Type RM Length L Ch R = 1,1350,203,203,203
BEGIN DESCRIPTION:
Stream0172 4.0
END DESCRIPTION:
XS GIS Cut Line= 4
      1822859.34     13935473.62      1822693.77     13935306.32
      1822563.78     13935295.24      1822392.01     13935311.69
#Sta/Elev= 30
  4695.3 1997.11  4768.1 1987.51  4775.2 1985.55  4817.6 1977.05  4838.8 1973.34
  4860.1 1968.77  4874.2 1966.78  4881.2 1964.93  4895.4 1959.82  4928.1 1952.21
  4949.5 1948.76  4959.6 1946.13  4989.7 1936.37  4999.7 1930.37  5007.9 1927.90
  5008.2 1927.40  5011.7 1927.40  5011.9 1927.90  5019.8 1933.80  5029.8 1940.25
  5058.0 1954.58  5061.1 1954.58  5080.0 1962.99  5108.1 1971.42  5113.1 1971.65
  5120.2 1974.75  5160.4 1987.07  5190.5 1992.55  5215.8 1995.81  5233.7 1997.18
#Mann=3,-1,0
  4695.3     0.1       0  5007.9    0.05       0  5011.9     0.1       0
Bank Sta=5007.9,5011.9
Exp/Cntr=0.3,0.1

Type RM Length L Ch R = 1,1147,205,205,205
BEGIN DESCRIPTION:
Stream0172 3.0
END DESCRIPTION:
XS GIS Cut Line= 3
      1823025.84     13935132.92      1822646.23     13935111.87
      1822409.95     13935204.27
#Sta/Elev= 30
  4648.9 2010.33  4698.2 2001.87  4703.2 2002.36  4709.8 2000.19  4790.0 1987.14
  4810.0 1980.48  4850.0 1969.72  4878.7 1963.05  4883.7 1963.71  4890.1 1960.62
  4930.2 1949.80  4970.2 1935.73  5000.3 1920.28  5008.3 1920.25  5008.5 1919.75
  5012.3 1920.25  5027.2 1932.46  5032.4 1932.46  5049.0 1939.81  5054.3 1939.90
  5073.4 1945.72  5078.8 1949.15  5094.8 1950.95  5103.3 1953.88  5116.3 1956.02
  5127.1 1958.78  5138.5 1963.63  5186.1 1970.35  5223.7 1978.44  5282.8 1988.34
#Mann=3,-1,0
  4648.9     0.1       0  5008.3    0.05       0  5012.3     0.1       0
Bank Sta=5008.3,5012.3
Exp/Cntr=0.3,0.1

Type RM Length L Ch R = 1,942,331,331,331
BEGIN DESCRIPTION:
Stream0172 2.0
END DESCRIPTION:
XS GIS Cut Line= 3
      1823032.81     13935042.20      1822725.00     13934925.00
      1822338.27     13934877.52
#Sta/Elev= 30
  4666.3 2013.12  4670.9 2011.23  4701.0 2006.90  4738.9 1998.84  4803.1 1988.44
  4846.2 1976.97  4895.7 1966.48  4925.8 1956.89  4974.3 1937.04  4980.6 1931.32
  4986.0 1930.08  4993.0 1924.25  4998.2 1924.25  5005.7 1916.18  5013.8 1914.34
  5014.1 1913.84  5017.8 1914.34  5025.9 1915.53  5033.8 1920.84  5046.0 1926.32
  5096.4 1940.57  5120.2 1944.50  5126.6 1947.72  5177.0 1956.63  5207.2 1965.38
  5277.8 1976.49  5287.9 1980.09  5318.1 1987.08  5348.3 1989.47  5385.3 1995.17
#Mann=3,-1,0
  4666.3     0.1       0  5013.8    0.05       0  5017.8     0.1       0
Bank Sta=5013.8,5017.8
Exp/Cntr=0.3,0.1

Type RM Length L Ch R = 1,611,249,249,249
BEGIN DESCRIPTION:
Stream0172 1.0
END DESCRIPTION:
XS GIS Cut Line= 3
      1823056.48     13934490.93      1822681.81     13934607.39
      1822412.10     13934699.63
#Sta/Elev= 30
  4600.6 2008.52  4732.6 1990.14  4765.2 1979.61  4835.5 1965.60  4884.9 1949.66
  4895.4 1947.93  4900.6 1945.27  4938.4 1935.57  4965.7 1924.98  4971.0 1924.90
  4986.3 1916.13  4988.7 1914.63  4993.0 1914.63  4997.9 1908.39  5008.7 1905.49
  5009.0 1904.99  5012.7 1905.49  5021.3 1908.32  5029.2 1914.10  5034.5 1916.29
  5042.4 1923.27  5053.0 1926.72  5060.6 1930.64  5084.7 1939.21  5128.4 1950.38
  5140.8 1955.02  5154.5 1959.71  5211.5 1970.72  5273.8 1985.93  5278.0 1985.93
#Mann=5,-1,0
  4600.6     0.1       0  4986.3    0.07       0  5008.7    0.05       0
  5012.7    0.07       0  5140.8     0.1       0
Bank Sta=5008.7,5012.7
Exp/Cntr=0.3,0.1

Type RM Length L Ch R = 1,362,161,161,161
BEGIN DESCRIPTION:
Stream0172 0.0
END DESCRIPTION:
XS GIS Cut Line= 4
      1823275.43     13934408.84      1822787.17     13934351.41
      1822448.32     13934404.53      1822239.43     13934678.33
#Sta/Elev= 30
  4344.2 2031.04  4503.1 2010.15  4515.8 2006.62  4626.6 1993.69  4762.4 1972.50
  4797.7 1965.09  4834.4 1952.33  4887.4 1936.64  4892.5 1936.67  4955.1 1912.98
  4960.2 1913.62  4979.7 1906.67  4989.9 1900.92  4998.0 1900.50  4998.2 1900.00
  5002.0 1900.50  5017.3 1912.79  5022.9 1913.63  5030.3 1918.86  5050.6 1926.69
  5091.1 1938.92  5121.4 1946.56  5182.3 1954.82  5193.9 1958.42  5209.9 1962.96
  5288.9 1973.33  5295.2 1976.44  5324.2 1978.60  5353.3 1985.37  5523.2 2004.41
#Mann=5,-1,0
  4344.2     0.1       0  4998.0    0.05       0  5002.0     0.1       0
  5017.3    0.07       0  5193.9     0.1       0
Bank Sta=4998,5002
Exp/Cntr=0.3,0.1

Type RM Length L Ch R = 1,201,0,0,0
BEGIN DESCRIPTION:
Stream0172 0.1
END DESCRIPTION:
XS GIS Cut Line= 4
      1823172.44     13934294.47      1822848.82     13934167.93
      1822480.81     13934247.51      1822292.54     13934435.56
#Sta/Elev= 30
  4423.7 1998.19  4515.3 1980.01  4520.7 1976.54  4569.6 1970.28  4629.3 1957.12
  4646.4 1957.93  4659.1 1952.65  4737.9 1941.69  4780.6 1931.28  4785.7 1934.40
  4824.7 1929.01  4829.8 1931.56  4873.9 1924.18  4879.1 1925.82  4923.2 1920.57
  4972.4 1907.24  4998.2 1891.48  4998.4 1890.98  5002.2 1891.48  5010.4 1894.90
  5016.5 1902.65  5041.1 1908.58  5115.0 1919.44  5150.0 1918.39  5157.1 1921.92
  5234.9 1936.30  5263.2 1943.87  5270.2 1948.44  5340.9 1966.75  5413.8 1976.88
#Mann=3,-1,0
  4423.7     0.1       0  4998.2    0.05       0  5002.2     0.1       0
Bank Sta=4998.2,5002.2
Exp/Cntr=0.3,0.1

Chan Stop Cuts=-1