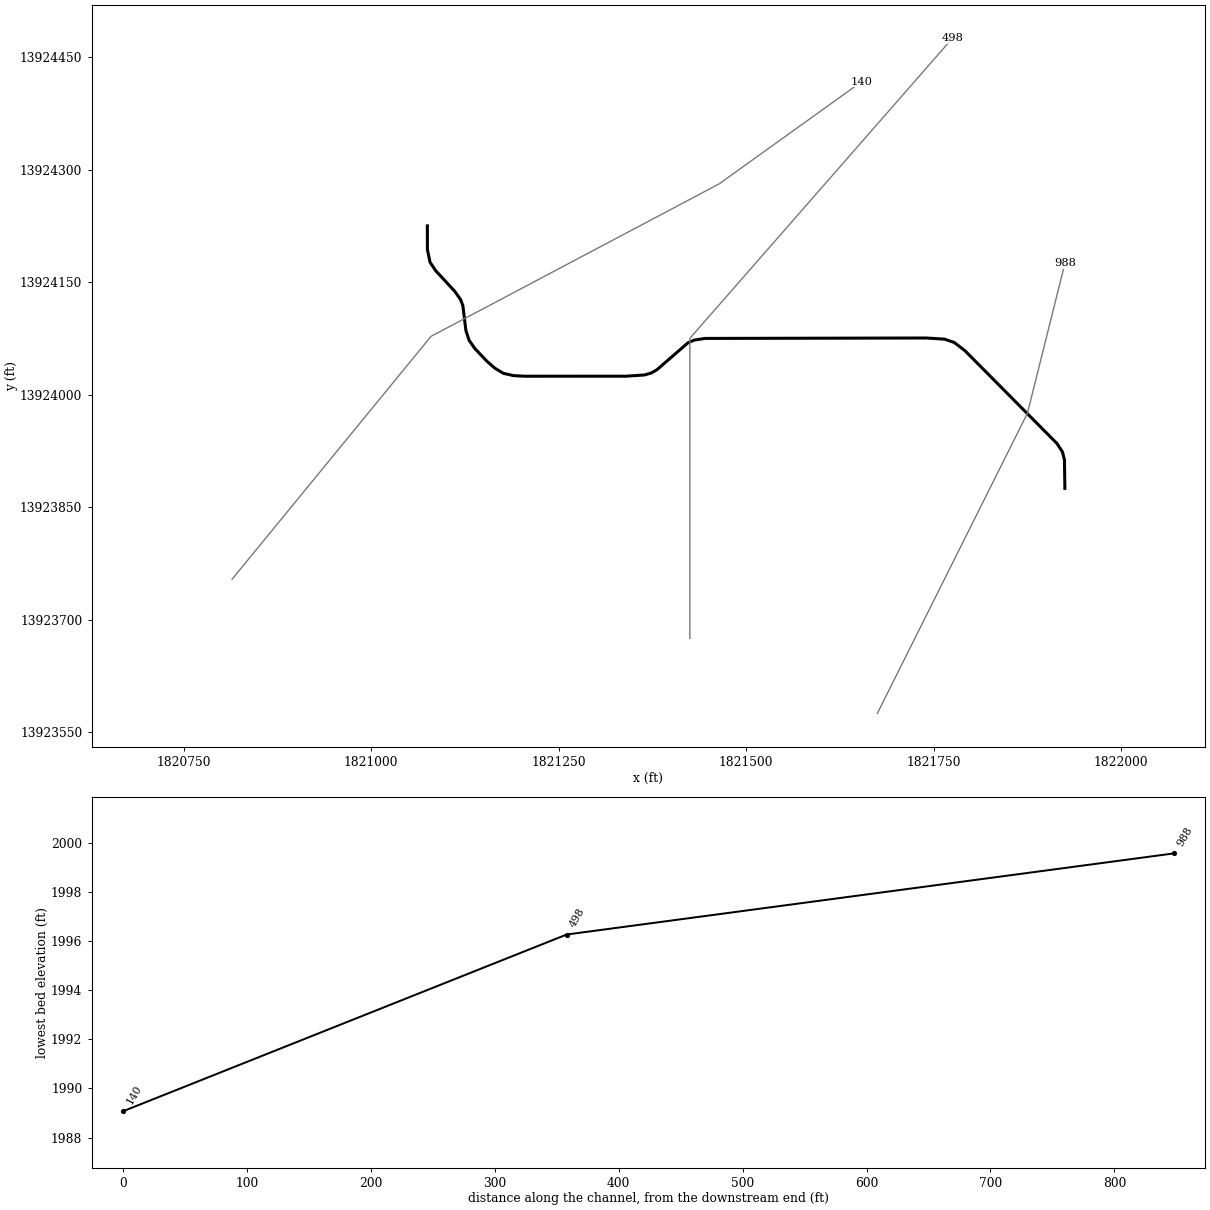
--- Stream0174.prj (project) ---

Proj Title=Stream0174 Base Level Engineering
Current Plan=p01
Default Exp/Contr=0.3,0.1
English Units
Geom File=g01
Flow File=f01
Plan File=p01
BEGIN DESCRIPTION:
Stream0174
END DESCRIPTION:

--- Stream0174.p01 (plan) ---

Plan Title=Multiple Run
Short Identifier=Multiple
Geom File=g01
Flow File=f01
Subcritical Flow
K Sum by GR= 0
Std Step Tol= 0.01
Critical Tol= 0.01
Num of Std Step Trials= 20
Max Error Tol= 0.3
Flow Tol Ratio= 0.001
Split Flow NTrial= 30
Split Flow Tol= 0.02
Split Flow Ratio= 0.02
Log Output Level= 0
Friction Slope Method= 1
Unsteady Friction Slope Method= 2
Unsteady Bridges Friction Slope Method= 1
Parabolic Critical Depth
Global Vel Dist=  1 , 1 , 1
Global Log Level= 0
CheckData=True
Encroach Param= -1, 0, 0, 0
BEGIN DESCRIPTION:
Multiple Run
END DESCRIPTION:

--- Stream0174.f01 (steady flow) ---

Flow Title=Multiple
Number of Profiles=7
Profile Names=10-year,25-year,50-year,1pct_min,100-year,1pct_plu,500-year
River Rch & RM= Stream0174,Reach-1,988
    1450    2539    3599    2464    4916    9808    9071
Boundary for River Rch & Prof#=Stream0174,Reach-1,1
Up Type=0
Dn Type=3
Dn Slope=0.005
Boundary for River Rch & Prof#=Stream0174,Reach-1,2
Up Type=0
Dn Type=3
Dn Slope=0.005
Boundary for River Rch & Prof#=Stream0174,Reach-1,3
Up Type=0
Dn Type=3
Dn Slope=0.005
Boundary for River Rch & Prof#=Stream0174,Reach-1,4
Up Type=0
Dn Type=3
Dn Slope=0.005
Boundary for River Rch & Prof#=Stream0174,Reach-1,5
Up Type=0
Dn Type=3
Dn Slope=0.005
Boundary for River Rch & Prof#=Stream0174,Reach-1,6
Up Type=0
Dn Type=3
Dn Slope=0.005
Boundary for River Rch & Prof#=Stream0174,Reach-1,7
Up Type=0
Dn Type=3
Dn Slope=0.005

--- Stream0174.g01 (geometry) ---

Geom Title=Existing Conditions

River Reach=Stream0174,Reach-1
Reach XY= 30
      1821925.00     13923875.00      1821924.41     13923913.16
      1821921.73     13923923.65      1821914.49     13923934.79
      1821791.77     13924058.57      1821777.45     13924069.54
      1821764.57     13924073.95      1821740.20     13924075.49
      1821445.03     13924074.93      1821430.94     13924072.74
      1821422.67     13924069.25      1821381.06     13924033.14
      1821373.43     13924028.78      1821364.49     13924026.22
      1821340.18     13924024.57      1821204.75     13924024.54
      1821190.03     13924025.33      1821176.25     13924028.44
      1821164.88     13924035.34      1821154.45     13924044.44
      1821138.44     13924061.36      1821130.69     13924072.40
      1821126.40     13924085.44      1821122.33     13924118.86
      1821119.01     13924127.21      1821111.21     13924138.13
      1821085.98     13924165.40      1821078.60     13924176.49
      1821075.10     13924193.19      1821075.00     13924225.00

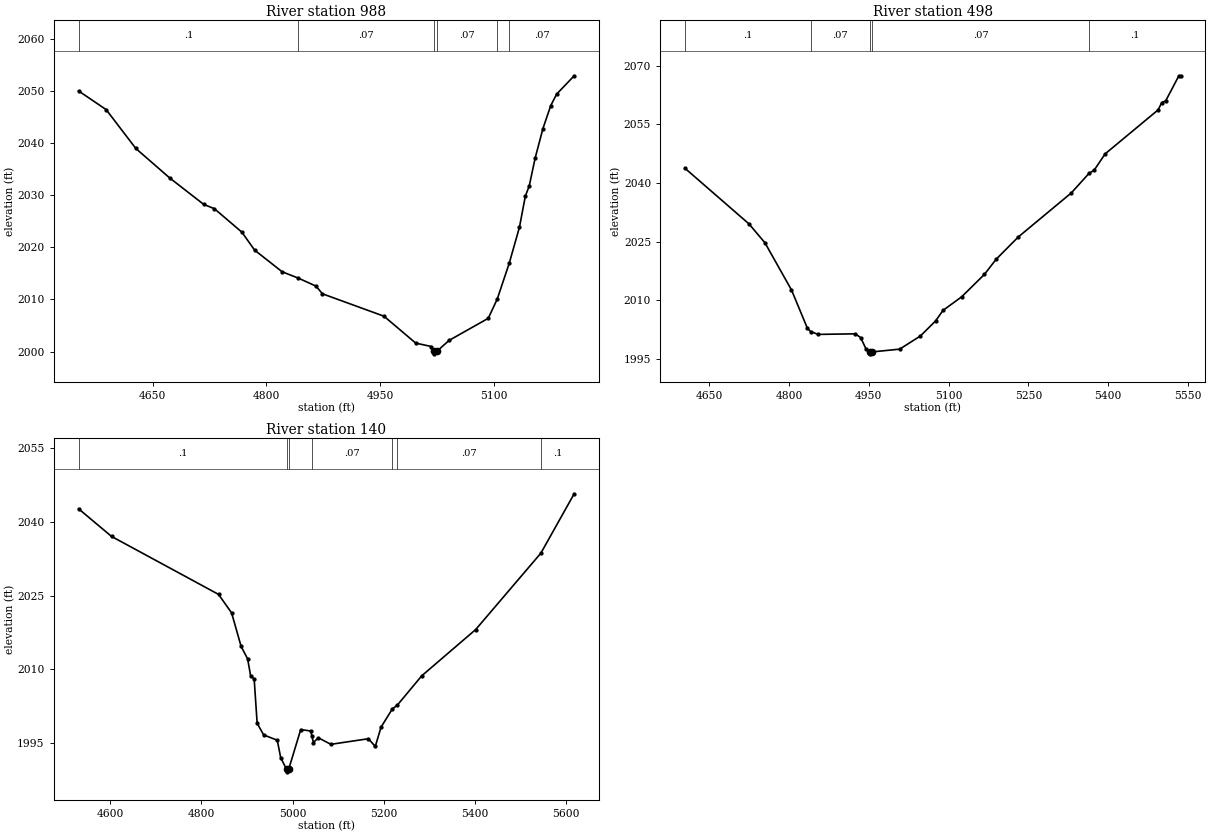
Type RM Length L Ch R = 1,988,490,490,490
BEGIN DESCRIPTION:
Stream0174 2.0
END DESCRIPTION:
XS GIS Cut Line= 3
      1821675.01     13923575.02      1821875.00     13923975.00
      1821924.99     13924174.95
#Sta/Elev= 30
  4552.6 2050.04  4588.9 2046.46  4628.0 2039.00  4672.8 2033.32  4717.5 2028.26
  4731.5 2027.44  4767.8 2022.93  4784.6 2019.48  4820.9 2015.32  4842.4 2014.09
  4865.6 2012.56  4874.0 2011.09  4955.1 2006.79  4997.0 2001.62  5017.8 2000.96
  5020.9 2000.06  5021.2 1999.56  5025.0 2000.06  5041.0 2002.14  5092.6 2006.38
  5104.4 2010.05  5120.2 2016.91  5133.8 2023.90  5141.5 2029.83  5146.7 2031.83
  5154.4 2037.12  5164.7 2042.82  5175.0 2047.23  5182.8 2049.44  5205.9 2052.96
#Mann=6,-1,0
  4552.6     0.1       0  4842.4    0.07       0  5020.9    0.05       0
  5025.0    0.07       0  5104.4     0.1       0  5120.2    0.07       0
Bank Sta=5020.9,5025
Exp/Cntr=0.3,0.1

Type RM Length L Ch R = 1,498,358,358,358
BEGIN DESCRIPTION:
Stream0174 1.0
END DESCRIPTION:
XS GIS Cut Line= 3
      1821425.00     13923675.03      1821425.00     13924075.00
      1821775.01     13924475.02
#Sta/Elev= 30
  4604.6 2043.74  4724.6 2029.54  4754.6 2024.71  4804.6 2012.62  4834.6 2002.77
  4840.7 2001.96  4854.6 2001.24  4924.6 2001.38  4934.6 2000.42  4944.6 1997.54
  4952.5 1996.76  4952.8 1996.26  4956.6 1996.76  5007.9 1997.46  5046.8 2000.82
  5075.3 2004.66  5089.5 2007.39  5124.6 2010.87  5167.3 2016.61  5189.2 2020.46
  5230.9 2026.18  5330.6 2037.46  5364.2 2042.51  5373.3 2043.23  5394.2 2047.46
  5493.8 2058.72  5500.5 2060.56  5508.1 2061.06  5532.8 2067.45  5536.1 2067.45
#Mann=5,-1,0
  4604.6     0.1       0  4840.7    0.07       0  4952.5    0.05       0
  4956.6    0.07       0  5364.2     0.1       0
Bank Sta=4952.5,4956.6
Exp/Cntr=0.3,0.1

Type RM Length L Ch R = 1,140,0,0,0
BEGIN DESCRIPTION:
Stream0174 0.0
END DESCRIPTION:
XS GIS Cut Line= 4
      1820814.65     13923753.85      1821079.95     13924077.71
      1821463.82     13924280.84      1821653.87     13924417.10
#Sta/Elev= 30
  4530.7 2042.69  4602.8 2037.07  4837.5 2025.25  4866.2 2021.48  4887.0 2014.66
  4901.3 2012.10  4907.8 2008.71  4915.7 2007.99  4922.2 1998.98  4936.5 1996.60
  4966.4 1995.51  4973.8 1991.97  4986.8 1989.57  4987.1 1989.07  4991.3 1989.57
  5017.8 1997.69  5039.8 1997.39  5042.5 1996.29  5045.6 1995.03  5056.2 1996.02
  5083.9 1994.68  5166.2 1995.82  5181.3 1994.24  5193.9 1998.17  5218.5 2001.87
  5230.0 2002.71  5283.2 2008.65  5401.5 2018.08  5544.5 2033.66  5617.5 2045.76
#Mann=7,-1,0
  4530.7     0.1       0  4986.8    0.05       0  4991.3     0.1       0
  5042.5    0.07       0  5218.5     0.1       0  5230.0    0.07       0
  5544.5     0.1       0
Bank Sta=4986.8,4991.3
Exp/Cntr=0.3,0.1

Chan Stop Cuts=-1