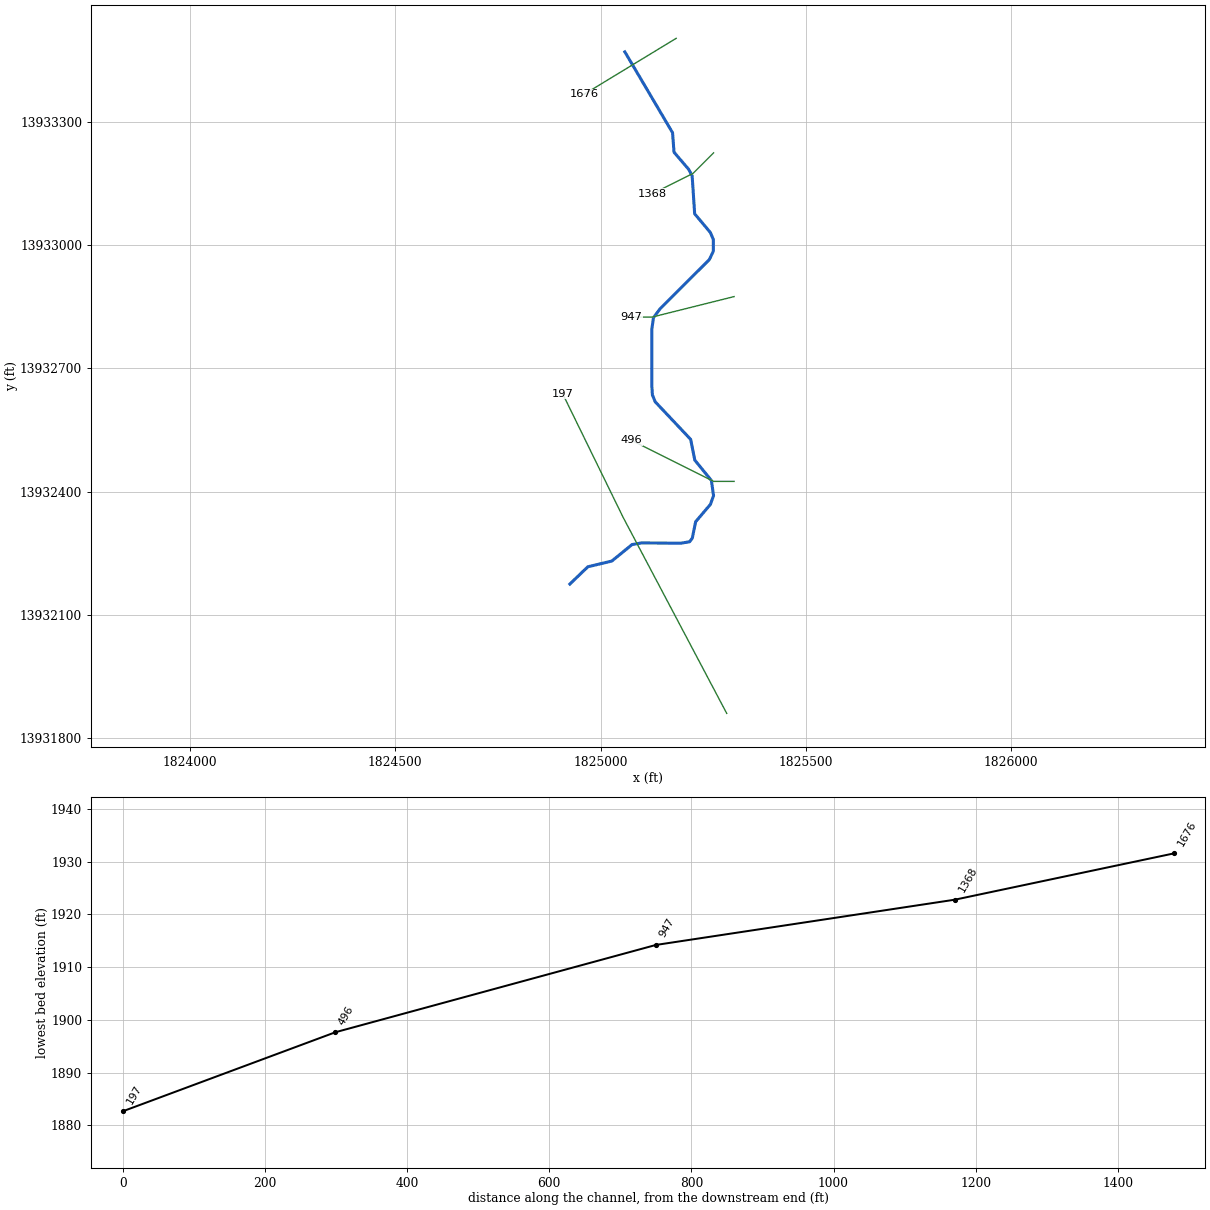
--- Stream0175.prj (project) ---

Proj Title=Stream0175 Base Level Engineering
Current Plan=p01
Default Exp/Contr=0.3,0.1
English Units
Geom File=g01
Flow File=f01
Plan File=p01
BEGIN DESCRIPTION:
Stream0175
END DESCRIPTION:

--- Stream0175.p01 (plan) ---

Plan Title=Multiple Run
Short Identifier=Multiple
Geom File=g01
Flow File=f01
Subcritical Flow
K Sum by GR= 0
Std Step Tol= 0.01
Critical Tol= 0.01
Num of Std Step Trials= 20
Max Error Tol= 0.3
Flow Tol Ratio= 0.001
Split Flow NTrial= 30
Split Flow Tol= 0.02
Split Flow Ratio= 0.02
Log Output Level= 0
Friction Slope Method= 1
Unsteady Friction Slope Method= 2
Unsteady Bridges Friction Slope Method= 1
Parabolic Critical Depth
Global Vel Dist=  1 , 1 , 1
Global Log Level= 0
CheckData=True
Encroach Param= -1, 0, 0, 0
BEGIN DESCRIPTION:
Multiple Run
END DESCRIPTION:

--- Stream0175.f01 (steady flow) ---

Flow Title=Multiple
Number of Profiles=7
Profile Names=10-year,25-year,50-year,1pct_min,100-year,1pct_plu,500-year
River Rch & RM= Stream0175,Reach-1,1676
     645    1075    1478     985    1965    3921    3427
Boundary for River Rch & Prof#=Stream0175,Reach-1,1
Up Type=0
Dn Type=3
Dn Slope=0.005
Boundary for River Rch & Prof#=Stream0175,Reach-1,2
Up Type=0
Dn Type=3
Dn Slope=0.005
Boundary for River Rch & Prof#=Stream0175,Reach-1,3
Up Type=0
Dn Type=3
Dn Slope=0.005
Boundary for River Rch & Prof#=Stream0175,Reach-1,4
Up Type=0
Dn Type=3
Dn Slope=0.005
Boundary for River Rch & Prof#=Stream0175,Reach-1,5
Up Type=0
Dn Type=3
Dn Slope=0.005
Boundary for River Rch & Prof#=Stream0175,Reach-1,6
Up Type=0
Dn Type=3
Dn Slope=0.005
Boundary for River Rch & Prof#=Stream0175,Reach-1,7
Up Type=0
Dn Type=3
Dn Slope=0.005

--- Stream0175.g01 (geometry) ---

Geom Title=Existing Conditions

River Reach=Stream0175,Reach-1
Reach XY= 30
      1825058.92     13933470.87      1825175.03     13933274.06
      1825178.64     13933226.51      1825214.39     13933184.75
      1825222.78     13933169.08      1825228.89     13933076.58
      1825267.21     13933030.91      1825274.28     13933014.29
      1825274.40     13932985.62      1825264.81     13932965.32
      1825144.61     13932845.16      1825128.54     13932823.54
      1825124.56     13932795.18      1825124.51     13932659.80
      1825126.05     13932635.44      1825132.83     13932618.81
      1825219.16     13932527.29      1825229.25     13932476.74
      1825269.67     13932427.19      1825274.94     13932390.37
      1825267.26     13932369.01      1825231.34     13932326.79
      1825223.07     13932286.68      1825216.72     13932278.07
      1825195.43     13932274.49      1825099.95     13932275.18
      1825076.56     13932271.25      1825027.22     13932231.03
      1824968.85     13932217.09      1824925.00     13932175.00

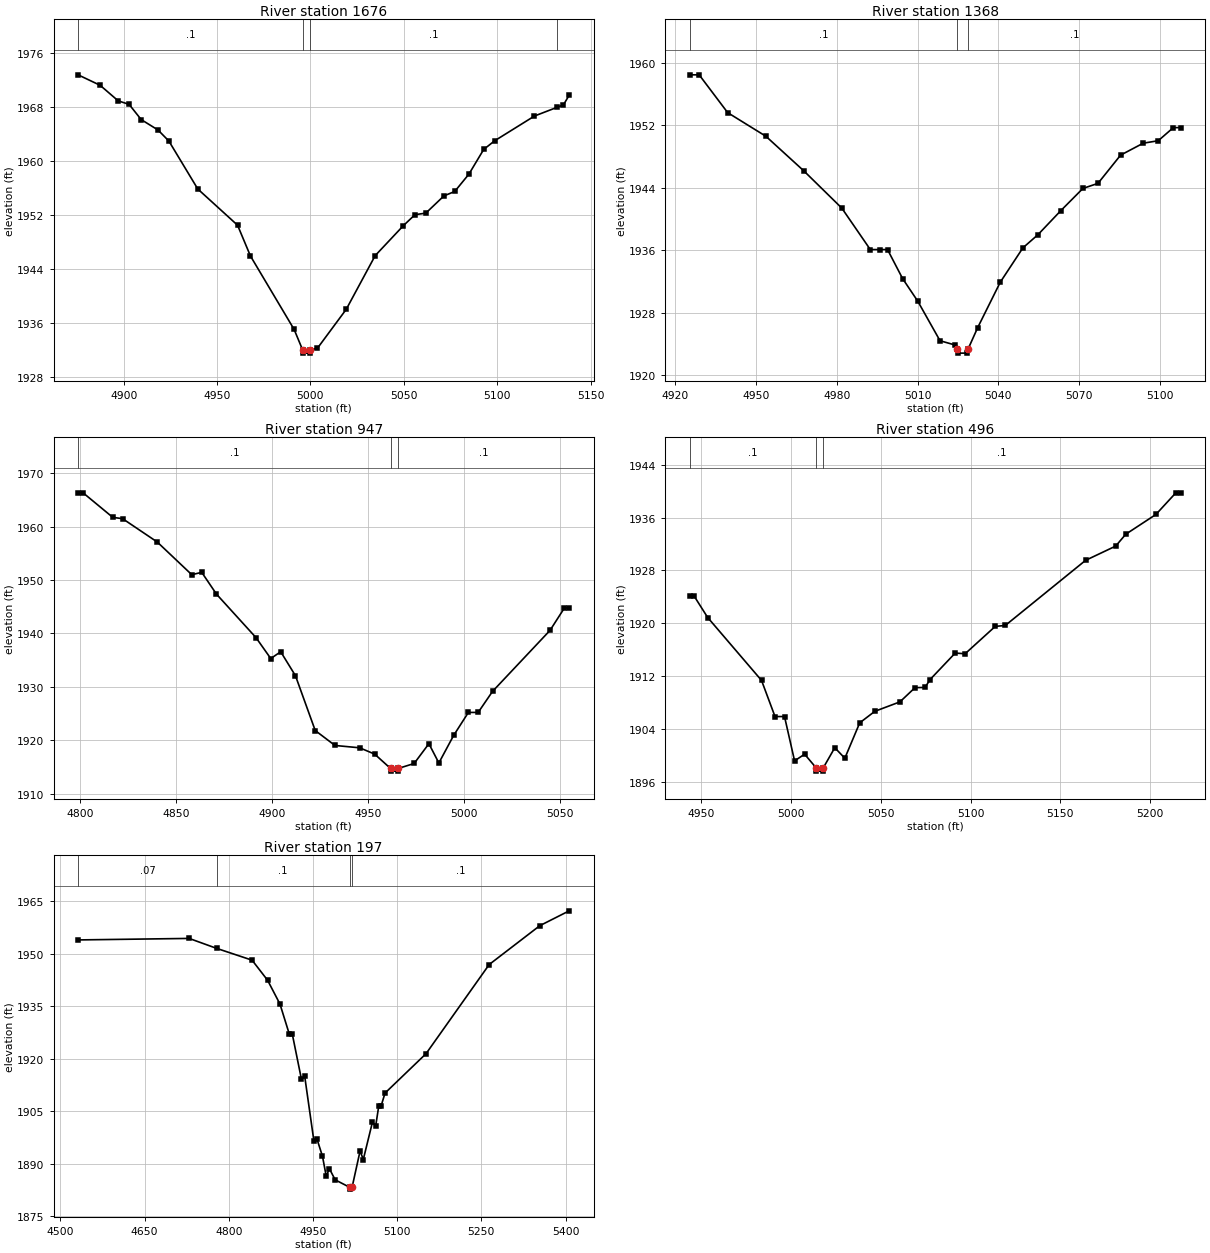
Type RM Length L Ch R = 1,1676,308,308,308
BEGIN DESCRIPTION:
Stream0175  4.0
END DESCRIPTION:
XS GIS Cut Line= 2
      1825183.90     13933503.83      1824959.14     13933367.25
#Sta/Elev= 30
  4875.6 1972.78  4887.4 1971.23  4897.1 1968.92  4902.9 1968.41  4909.4 1966.15
  4918.4 1964.61  4924.2 1962.98  4939.7 1955.87  4961.0 1950.51  4967.9 1945.95
  4991.3 1935.07  4995.8 1932.07  4996.1 1931.57  4999.6 1931.57  4999.8 1932.07
  5003.7 1932.27  5019.2 1938.06  5034.7 1946.01  5049.8 1950.45  5056.0 1952.07
  5061.8 1952.30  5071.5 1954.85  5077.3 1955.51  5084.9 1958.08  5092.8 1961.73
  5098.6 1963.00  5120.0 1966.68  5132.3 1967.99  5135.5 1968.33  5138.6 1969.77
#Mann=4,-1,0
  4875.6     0.1       0  4995.8    0.05       0  4999.8     0.1       0
  5132.3    0.07       0
Bank Sta=4995.8,4999.8
Exp/Cntr=0.3,0.1

Type RM Length L Ch R = 1,1368,421,421,421
BEGIN DESCRIPTION:
Stream0175 3.0
END DESCRIPTION:
XS GIS Cut Line= 3
      1825274.98     13933224.98      1825225.00     13933175.00
      1825124.98     13933124.99
#Sta/Elev= 29
  4925.3 1958.49  4928.8 1958.49  4939.4 1953.64  4953.6 1950.61  4967.7 1946.17
  4981.8 1941.40  4992.4 1936.08  4996.0 1936.08  4998.8 1936.08  5004.4 1932.36
  5010.0 1929.48  5018.3 1924.39  5023.9 1923.84  5024.7 1923.30  5025.0 1922.80
  5028.5 1922.80  5028.7 1923.30  5032.3 1926.07  5040.7 1931.90  5049.1 1936.30
  5054.7 1937.99  5063.1 1941.04  5071.4 1943.92  5077.0 1944.57  5085.4 1948.19
  5093.8 1949.72  5099.4 1950.04  5105.0 1951.72  5107.8 1951.72
#Mann=3,-1,0
  4925.3     0.1       0  5024.7    0.05       0  5028.7     0.1       0
Bank Sta=5024.7,5028.7
Exp/Cntr=0.3,0.1

Type RM Length L Ch R = 1,947,451,451,451
BEGIN DESCRIPTION:
Stream0175 2.0
END DESCRIPTION:
XS GIS Cut Line= 3
      1825325.04     13932875.01      1825125.00     13932825.00
      1825075.00     13932825.00
#Sta/Elev= 30
  4798.8 1966.36  4801.4 1966.36  4816.9 1961.76  4822.0 1961.52  4840.1 1957.14
  4858.1 1951.02  4863.3 1951.46  4871.0 1947.37  4891.6 1939.23  4899.3 1935.31
  4904.5 1936.58  4912.2 1932.08  4922.5 1921.82  4932.8 1919.02  4945.7 1918.58
  4953.5 1917.40  4961.8 1914.71  4962.0 1914.21  4965.5 1914.21  4965.8 1914.71
  4974.1 1915.64  4981.8 1919.35  4987.0 1915.74  4994.7 1920.89  5002.4 1925.21
  5007.5 1925.21  5015.0 1929.15  5045.0 1940.59  5052.5 1944.79  5055.0 1944.79
#Mann=3,-1,0
  4798.8     0.1       0  4961.8    0.05       0  4965.8     0.1       0
Bank Sta=4961.8,4965.8
Exp/Cntr=0.3,0.1

Type RM Length L Ch R = 1,496,299,299,299
BEGIN DESCRIPTION:
Stream0175 1.0
END DESCRIPTION:
XS GIS Cut Line= 3
      1825325.03     13932425.00      1825275.00     13932425.00
      1825075.03     13932524.98
#Sta/Elev= 30
  4943.5 1924.10  4946.0 1924.10  4953.5 1920.88  4983.5 1911.37  4991.0 1905.91
  4996.3 1905.91  5001.9 1899.21  5007.5 1900.22  5013.9 1898.16  5014.1 1897.66
  5017.6 1897.66  5017.9 1898.16  5024.3 1901.20  5029.9 1899.61  5038.2 1904.96
  5046.6 1906.70  5060.6 1908.13  5069.0 1910.28  5074.6 1910.31  5077.4 1911.51
  5091.4 1915.51  5096.9 1915.40  5113.7 1919.54  5119.3 1919.68  5164.0 1929.52
  5180.8 1931.68  5186.4 1933.47  5203.2 1936.46  5214.3 1939.73  5217.1 1939.73
#Mann=3,-1,0
  4943.5     0.1       0  5013.9    0.05       0  5017.9     0.1       0
Bank Sta=5013.9,5017.9
Exp/Cntr=0.3,0.1

Type RM Length L Ch R = 1,197,0,0,0
BEGIN DESCRIPTION:
Stream0175 0.0
END DESCRIPTION:
XS GIS Cut Line= 3
      1825306.93     13931860.12      1825054.76     13932337.38
      1824907.55     13932638.32
#Sta/Elev= 30
  4531.7 1953.93  4729.5 1954.36  4778.4 1951.52  4841.6 1948.14  4869.2 1942.41
  4891.3 1935.59  4907.6 1927.16  4913.3 1926.96  4929.6 1914.03  4935.3 1914.99
  4951.6 1896.57  4957.3 1896.94  4967.0 1892.08  4973.7 1886.35  4979.3 1888.53
  4989.6 1885.34  5015.7 1883.18  5015.9 1882.68  5019.7 1883.18  5034.0 1893.61
  5039.7 1891.15  5056.1 1901.89  5061.7 1900.66  5067.3 1906.49  5071.5 1906.49
  5078.4 1910.14  5151.5 1921.41  5264.0 1946.90  5354.1 1958.00  5406.5 1962.25
#Mann=4,-1,0
  4531.7    0.07       0  4778.4     0.1       0  5015.7    0.05       0
  5019.7     0.1       0
Bank Sta=5015.7,5019.7
Exp/Cntr=0.3,0.1

Chan Stop Cuts=-1