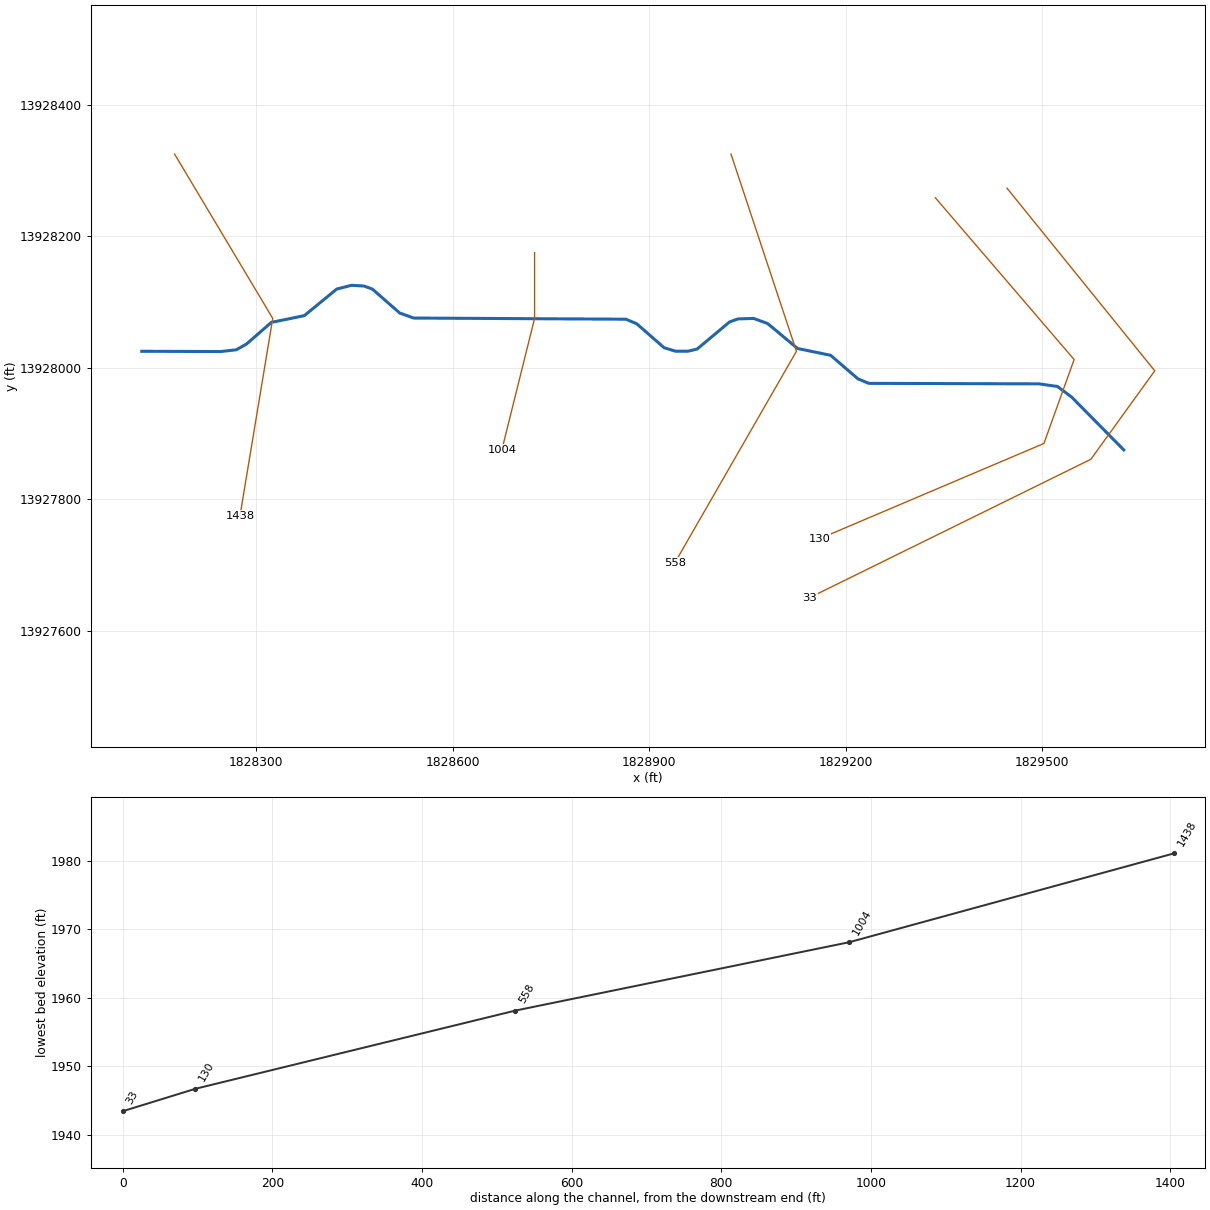
--- Stream0177.prj (project) ---

Proj Title=Stream0177 Base Level Engineering
Current Plan=p01
Default Exp/Contr=0.3,0.1
English Units
Geom File=g01
Flow File=f01
Plan File=p01
Y Axis Title=Elevation
X Axis Title(PF)=Main Channel Distance
X Axis Title(XS)=Station
BEGIN DESCRIPTION:
Stream0177
END DESCRIPTION:
DSS Export Rating Curves= 0
DSS Export Rating Curve Sorted= 0
DSS Export Volume Flow Curves= 0
DXF OffsetX= 0
DXF OffsetY= 0
DXF ScaleX= 1
DXF ScaleY= 10

--- Stream0177.p01 (plan) ---

Plan Title=Multiple Run
Short Identifier=Multiple
Geom File=g01
Flow File=f01
Subcritical Flow
K Sum by GR= 0
Std Step Tol= 0.01
Critical Tol= 0.01
Num of Std Step Trials= 20
Max Error Tol= 0.3
Flow Tol Ratio= 0.001
Split Flow NTrial= 30
Split Flow Tol= 0.02
Split Flow Ratio= 0.02
Log Output Level= 0
Friction Slope Method= 1
Unsteady Friction Slope Method= 2
Unsteady Bridges Friction Slope Method= 1
Parabolic Critical Depth
Global Vel Dist=  1 , 1 , 1
Global Log Level= 0
CheckData=True
Encroach Param= -1, 0, 0, 0
BEGIN DESCRIPTION:
Multiple Run
END DESCRIPTION:

--- Stream0177.f01 (steady flow) ---

Flow Title=Multiple
Program Version=4.10
Number of Profiles= 7
Profile Names=10-year,25-year,50-year,1pct_min,100-year,1pct_plu,500-year
River Rch & RM=Stream0177,Reach-1         ,1438
     432     701     946     620    1238    2469    2084
Boundary for River Rch & Prof#=Stream0177,Reach-1         , 1
Up Type= 0
Dn Type= 3
Dn Slope=0.005
Boundary for River Rch & Prof#=Stream0177,Reach-1         , 2
Up Type= 0
Dn Type= 3
Dn Slope=0.005
Boundary for River Rch & Prof#=Stream0177,Reach-1         , 3
Up Type= 0
Dn Type= 3
Dn Slope=0.005
Boundary for River Rch & Prof#=Stream0177,Reach-1         , 4
Up Type= 0
Dn Type= 3
Dn Slope=0.005
Boundary for River Rch & Prof#=Stream0177,Reach-1         , 5
Up Type= 0
Dn Type= 3
Dn Slope=0.005
Boundary for River Rch & Prof#=Stream0177,Reach-1         , 6
Up Type= 0
Dn Type= 3
Dn Slope=0.005
Boundary for River Rch & Prof#=Stream0177,Reach-1         , 7
Up Type= 0
Dn Type= 3
Dn Slope=0.005
DSS Import GetInterval= 0
DSS Import GetPeak= 0
DSS Import FillOption= 0

--- Stream0177.g01 (geometry) ---

Geom Title=Existing Conditions

River Reach=Stream0177,Reach-1
Reach XY= 30
      1828125.00     13928025.00      1828245.18     13928024.56
      1828269.09     13928027.20      1828284.67     13928035.79
      1828322.82     13928068.89      1828373.28     13928079.22
      1828422.80     13928119.66      1828445.17     13928125.29
      1828464.31     13928124.24      1828477.18     13928119.63
      1828518.92     13928083.19      1828540.21     13928075.54
      1828864.50     13928073.76      1828881.08     13928066.81
      1828922.82     13928030.38      1828940.40     13928025.10
      1828959.61     13928025.11      1828973.28     13928028.40
      1829022.80     13928069.59      1829035.69     13928074.22
      1829059.61     13928074.92      1829080.94     13928067.23
      1829126.72     13928029.22      1829177.18     13928018.89
      1829218.92     13927983.10      1829235.50     13927976.20
      1829495.18     13927975.43      1829523.56     13927971.52
      1829545.21     13927955.50      1829625.00     13927875.00

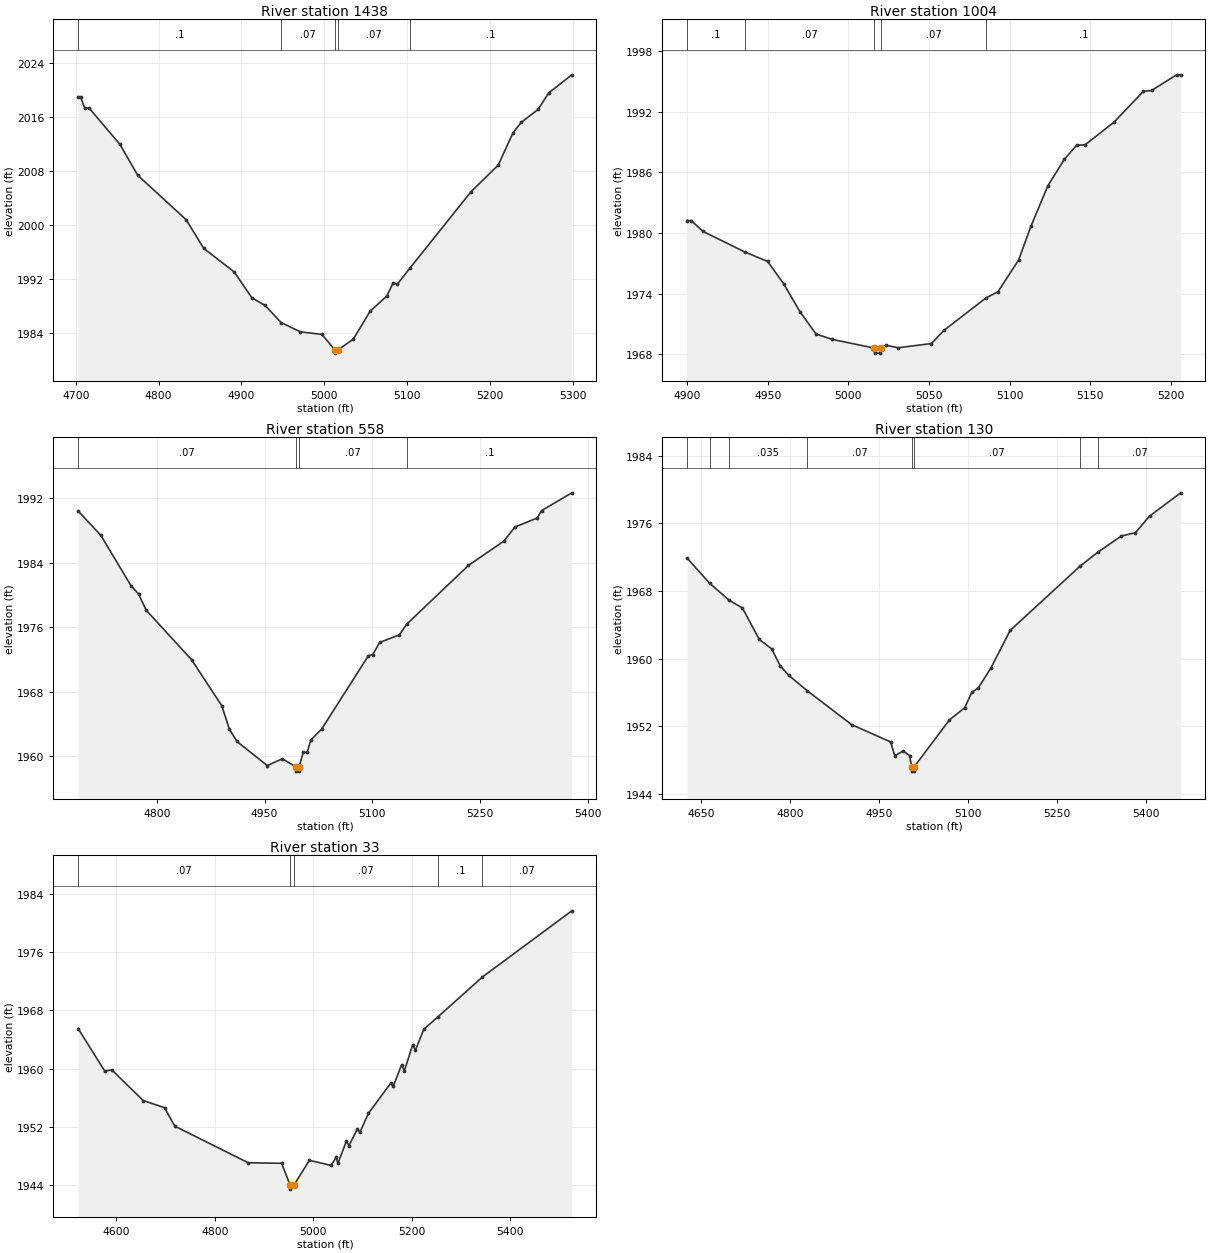
Type RM Length L Ch R = 1,1438,434,434,434
BEGIN DESCRIPTION:
Stream0177 3.0
END DESCRIPTION:
XS GIS Cut Line= 3
      1828175.01     13928324.99      1828325.00     13928075.00
      1828275.00     13927774.98
#Sta/Elev= 30
  4702.9 2019.01  4705.8 2019.01  4710.7 2017.38  4716.5 2017.29  4753.4 2011.95
  4774.8 2007.39  4833.1 2000.83  4854.5 1996.57  4891.4 1993.06  4912.8 1989.21
  4928.4 1988.14  4947.9 1985.58  4971.1 1984.21  4997.0 1983.83  5012.7 1981.56
  5013.0 1981.06  5016.7 1981.56  5035.0 1983.13  5055.3 1987.27  5075.5 1989.52
  5083.1 1991.47  5088.2 1991.27  5103.4 1993.66  5176.9 2004.93  5209.9 2008.90
  5227.6 2013.66  5237.7 2015.23  5258.0 2017.13  5270.7 2019.57  5298.6 2022.25
#Mann=5,-1,0
  4702.9     0.1       0  4947.9    0.07       0  5012.7    0.05       0
  5016.7    0.07       0  5103.4     0.1       0
Bank Sta=5012.7,5016.7
Exp/Cntr=0.3,0.1

Type RM Length L Ch R = 1,1004,446,446,446
BEGIN DESCRIPTION:
Stream0177 2.0
END DESCRIPTION:
XS GIS Cut Line= 3
      1828725.00     13928175.01      1828725.00     13928075.00
      1828674.99     13927874.97
#Sta/Elev= 30
  4900.0 1981.22  4902.5 1981.22  4910.0 1980.14  4935.7 1978.12  4950.0 1977.17
  4960.0 1974.95  4970.0 1972.21  4980.0 1969.99  4990.0 1969.46  5016.1 1968.60
  5016.3 1968.10  5019.8 1968.10  5020.1 1968.60  5023.2 1968.89  5030.9 1968.63
  5051.6 1969.05  5059.3 1970.35  5085.4 1973.56  5092.8 1974.16  5105.7 1977.33
  5113.4 1980.70  5123.7 1984.63  5134.0 1987.28  5141.7 1988.68  5146.9 1988.71
  5164.9 1990.97  5183.0 1994.00  5188.1 1994.09  5203.6 1995.64  5206.2 1995.64
#Mann=5,-1,0
  4900.0     0.1       0  4935.7    0.07       0  5016.1    0.05       0
  5020.1    0.07       0  5085.4     0.1       0
Bank Sta=5016.1,5020.1
Exp/Cntr=0.3,0.1

Type RM Length L Ch R = 1,558,428,428,428
BEGIN DESCRIPTION:
Stream0177 1.0
END DESCRIPTION:
XS GIS Cut Line= 3
      1829025.01     13928324.97      1829125.00     13928025.00
      1828939.25     13927703.27
#Sta/Elev= 30
  4690.2 1990.43  4721.8 1987.41  4764.0 1981.14  4774.5 1980.12  4785.0 1978.11
  4848.3 1971.96  4890.4 1966.24  4901.0 1963.33  4911.5 1961.81  4953.7 1958.82
  4974.8 1959.67  4993.9 1958.63  4994.1 1958.13  4997.6 1958.13  4997.9 1958.63
  5003.8 1960.45  5009.3 1960.45  5014.3 1961.98  5029.5 1963.36  5094.7 1972.47
  5100.5 1972.58  5110.3 1974.11  5137.8 1975.05  5148.0 1976.38  5234.0 1983.67
  5283.5 1986.70  5298.6 1988.43  5329.7 1989.56  5335.9 1990.48  5377.9 1992.68
#Mann=4,-1,0
  4690.2    0.07       0  4993.9    0.05       0  4997.9    0.07       0
  5148.0     0.1       0
Bank Sta=4993.9,4997.9
Exp/Cntr=0.3,0.1

Type RM Length L Ch R = 1,130,97,97,97
BEGIN DESCRIPTION:
Stream0177 0.0
END DESCRIPTION:
XS GIS Cut Line= 4
      1829337.23     13928258.46      1829549.20     13928012.45
      1829503.05     13927884.77      1829160.51     13927739.95
#Sta/Elev= 30
  4626.2 1971.89  4664.4 1968.90  4697.6 1966.88  4719.5 1966.00  4748.0 1962.27
  4768.8 1961.17  4783.1 1959.18  4797.4 1958.05  4828.7 1956.22  4903.8 1952.20
  4969.5 1950.16  4976.4 1948.53  4990.8 1949.10  5001.4 1948.54  5005.1 1947.21
  5005.3 1946.71  5008.8 1946.71  5009.1 1947.21  5068.4 1952.75  5094.5 1954.21
  5106.3 1956.03  5117.2 1956.53  5138.9 1958.95  5171.0 1963.34  5288.8 1970.93
  5319.2 1972.60  5358.6 1974.50  5382.3 1974.89  5406.0 1976.85  5458.6 1979.60
#Mann=8,-1,0
  4626.2   0.035       0  4664.4    0.07       0  4697.6   0.035       0
  4828.7    0.07       0  5005.1    0.05       0  5009.1    0.07       0
  5288.8     0.1       0  5319.2    0.07       0
Bank Sta=5005.1,5009.1
Exp/Cntr=0.3,0.1

Type RM Length L Ch R = 1,33,0,0,0
BEGIN DESCRIPTION:
Stream0177 0.1
END DESCRIPTION:
XS GIS Cut Line= 4
      1829446.70     13928273.02      1829672.38     13927995.26
      1829574.72     13927860.71      1829145.06     13927650.22
#Sta/Elev= 30
  4522.2 1965.52  4576.3 1959.67  4590.7 1959.83  4654.6 1955.61  4697.7 1954.64
  4718.6 1952.10  4867.5 1947.07  4935.6 1946.99  4953.0 1943.94  4953.5 1943.44
  4959.9 1943.94  4992.0 1947.40  5036.1 1946.70  5046.3 1947.85  5049.8 1946.97
  5066.7 1949.99  5072.3 1949.42  5089.2 1951.68  5094.8 1951.29  5111.7 1953.85
  5156.7 1957.97  5162.3 1957.60  5179.2 1960.52  5184.8 1959.69  5201.7 1963.30
  5207.3 1962.53  5224.2 1965.42  5253.4 1967.15  5343.2 1972.60  5524.8 1981.70
#Mann=5,-1,0
  4522.2    0.07       0  4953.0    0.05       0  4959.9    0.07       0
  5253.4     0.1       0  5343.2    0.07       0
Bank Sta=4953,4959.9
Exp/Cntr=0.3,0.1

Chan Stop Cuts=-1