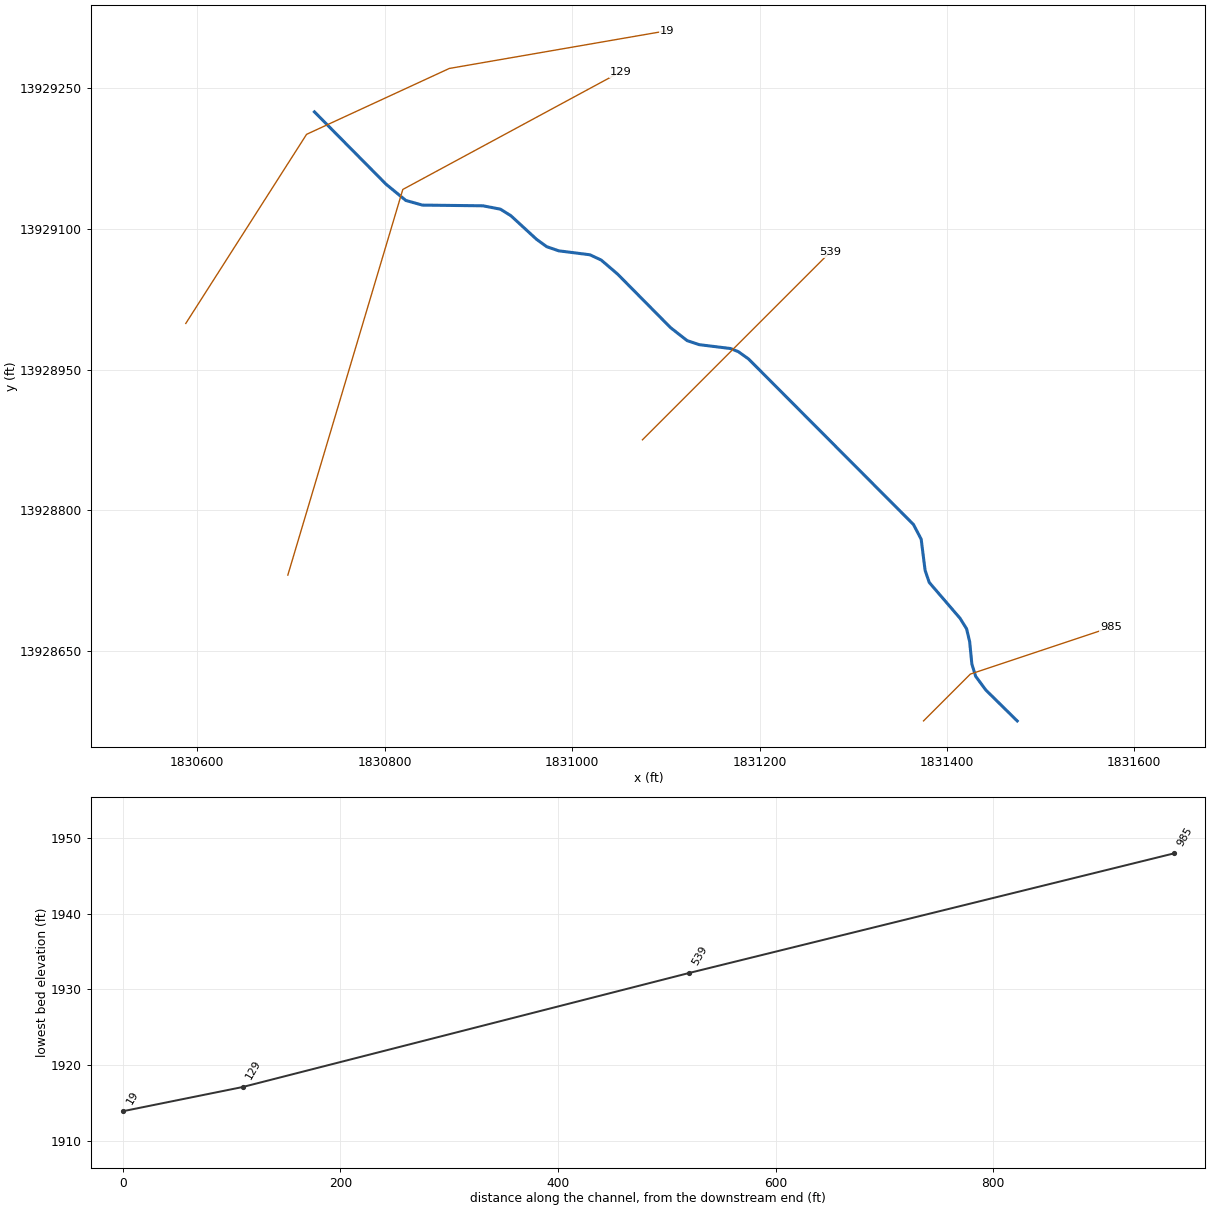
--- Stream0178.prj (project) ---

Proj Title=Stream0178 Base Level Engineering
Current Plan=p01
Default Exp/Contr=0.3,0.1
English Units
Geom File=g01
Flow File=f01
Plan File=p01
Y Axis Title=Elevation
X Axis Title(PF)=Main Channel Distance
X Axis Title(XS)=Station
BEGIN DESCRIPTION:
Stream0178
END DESCRIPTION:
DSS Export Rating Curves= 0
DSS Export Rating Curve Sorted= 0
DSS Export Volume Flow Curves= 0
DXF OffsetX= 0
DXF OffsetY= 0
DXF ScaleX= 1
DXF ScaleY= 10

--- Stream0178.p01 (plan) ---

Plan Title=Multiple Run
Short Identifier=Multiple
Geom File=g01
Flow File=f01
Subcritical Flow
K Sum by GR= 0
Std Step Tol= 0.01
Critical Tol= 0.01
Num of Std Step Trials= 20
Max Error Tol= 0.3
Flow Tol Ratio= 0.001
Split Flow NTrial= 30
Split Flow Tol= 0.02
Split Flow Ratio= 0.02
Log Output Level= 0
Friction Slope Method= 1
Unsteady Friction Slope Method= 2
Unsteady Bridges Friction Slope Method= 1
Parabolic Critical Depth
Global Vel Dist=  1 , 1 , 1
Global Log Level= 0
CheckData=True
Encroach Param= -1, 0, 0, 0
BEGIN DESCRIPTION:
Multiple Run
END DESCRIPTION:

--- Stream0178.f01 (steady flow) ---

Flow Title=Multiple
Program Version=4.10
Number of Profiles= 7
Profile Names=10-year,25-year,50-year,1pct_min,100-year,1pct_plu,500-year
River Rch & RM=Stream0178,Reach-1         ,985
     342     546     731     476     949    1894    1574
Boundary for River Rch & Prof#=Stream0178,Reach-1         , 1
Up Type= 0
Dn Type= 3
Dn Slope=0.03
Boundary for River Rch & Prof#=Stream0178,Reach-1         , 2
Up Type= 0
Dn Type= 3
Dn Slope=0.03
Boundary for River Rch & Prof#=Stream0178,Reach-1         , 3
Up Type= 0
Dn Type= 3
Dn Slope=0.03
Boundary for River Rch & Prof#=Stream0178,Reach-1         , 4
Up Type= 0
Dn Type= 3
Dn Slope=0.03
Boundary for River Rch & Prof#=Stream0178,Reach-1         , 5
Up Type= 0
Dn Type= 3
Dn Slope=0.03
Boundary for River Rch & Prof#=Stream0178,Reach-1         , 6
Up Type= 0
Dn Type= 3
Dn Slope=0.03
Boundary for River Rch & Prof#=Stream0178,Reach-1         , 7
Up Type= 0
Dn Type= 3
Dn Slope=0.03
DSS Import GetInterval= 0
DSS Import GetPeak= 0
DSS Import FillOption= 0

--- Stream0178.g01 (geometry) ---

Geom Title=Existing Conditions
Program Version=4.10

River Reach=Stream0178      ,Reach-1
Reach XY= 30
        1831475.       13928575.      1831441.41     13928608.07
      1831430.67     13928622.64       1831426.6     13928635.66
      1831424.23     13928659.68      1831420.96     13928673.33
      1831413.96     13928684.57       1831381.1     13928722.81
       1831376.7      13928735.7       1831372.5     13928768.97
      1831364.24     13928784.68      1831188.21     13928961.37
      1831177.29     13928969.14      1831168.95     13928972.47
      1831135.64     13928976.56      1831122.72     13928980.87
      1831104.93     13928994.83      1831048.45     13929051.94
      1831031.05     13929066.84      1831018.96      13929072.5
      1830985.71     13929076.72      1830972.83     13929081.14
      1830961.96     13929089.05      1830934.65     13929114.16
      1830923.42     13929121.17       1830904.9     13929124.77
      1830840.21     13929125.51      1830822.55     13929130.46
      1830801.43     13929147.77        1830725.       13929225.

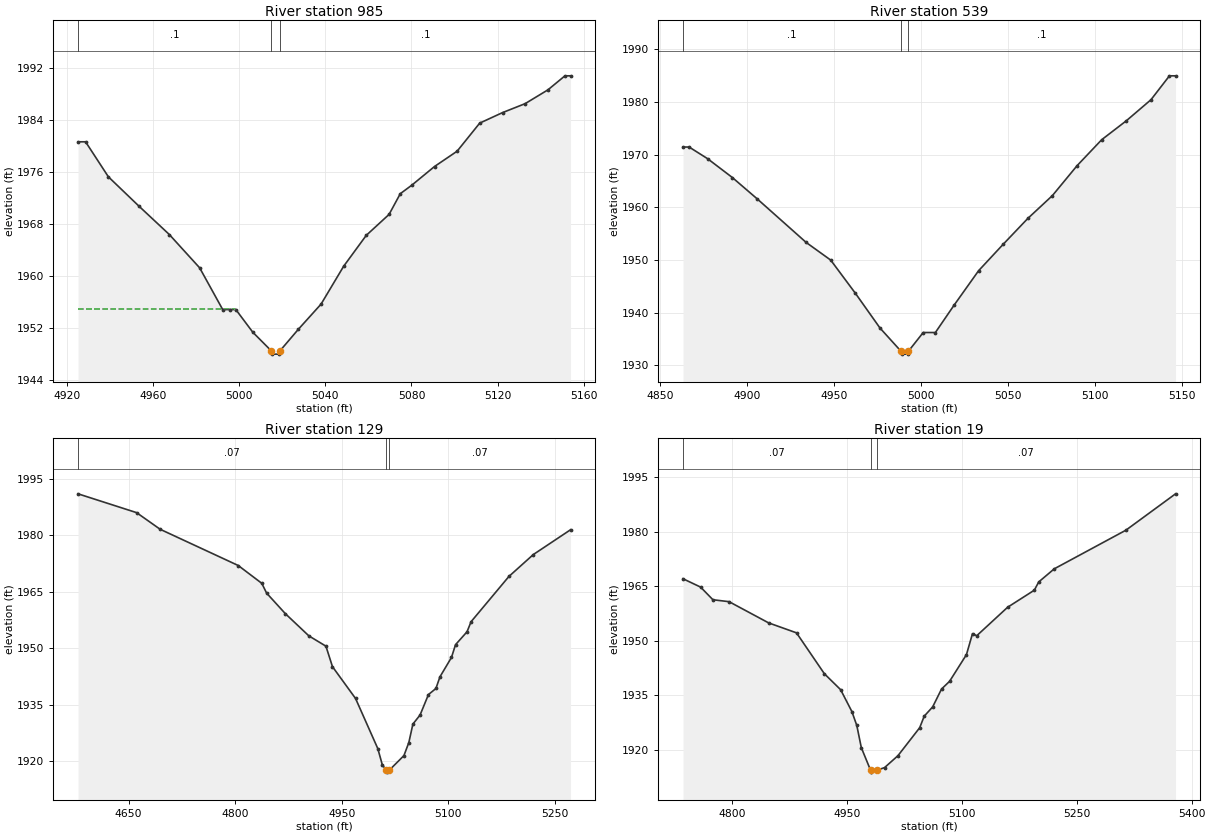
Type RM Length L Ch R = 1 ,985     ,446,446,446
BEGIN DESCRIPTION:
Stream0178 2.0
END DESCRIPTION:
XS GIS Cut Line= 3
      1831375.01     13928575.01        1831425.       13928625.
        1831575.       13928675.
#Sta/Elev= 29
  4925.1 1980.66  4928.6 1980.66  4939.2 1975.26  4953.4 1970.74  4967.5 1966.37
  4981.6 1961.23  4992.3  1954.8  4995.8  1954.8  4998.4  1954.8  5006.3  1951.3
  5014.9 1948.43  5015.1 1947.93  5018.6 1947.93  5018.9 1948.43  5027.4 1951.74
    5038 1955.64  5048.5 1961.48    5059 1966.24  5069.6 1969.47  5074.8 1972.66
  5080.1 1973.96  5090.7 1976.85  5101.2 1979.21  5111.7 1983.54  5122.3 1985.16
  5132.8 1986.54  5143.4 1988.67  5151.3 1990.83  5153.9 1990.83
#Mann= 3 ,-1 , 0
  4925.1      .1       0  5014.9     .04       0  5018.9      .1       0
#XS Ineff= 2 , 0
         4998.06 1954.95
Permanent Ineff=
       F       F
Bank Sta=5014.9,5018.9
XS Rating Curve= 0 ,0
Exp/Cntr=0.3,0.1

Type RM Length L Ch R = 1 ,539     ,410,410,410
BEGIN DESCRIPTION:
Stream0178 1.0
END DESCRIPTION:
XS GIS Cut Line= 3
      1831075.01     13928875.01        1831175.       13928975.
      1831274.98     13929074.98
#Sta/Elev= 26
  4863.4 1971.43  4866.9 1971.43  4877.5 1969.22  4891.7 1965.65  4905.8 1961.65
  4934.1 1953.33  4948.2 1949.98  4962.4 1943.67  4976.5 1937.09  4988.7 1932.64
  4988.9 1932.14  4992.4 1932.14  4992.7 1932.64  5001.3 1936.24  5008.3 1936.24
    5019 1941.41  5033.1 1947.96  5047.2 1952.97  5061.4 1957.89  5075.5 1962.22
  5089.7 1967.91  5103.8 1972.82  5117.9  1976.4  5132.1 1980.41  5142.7 1984.94
  5146.2 1984.94
#Mann= 3 ,-1 , 0
  4863.4      .1       0  4988.7     .04       0  4992.7      .1       0
Bank Sta=4988.7,4992.7
XS Rating Curve= 0 ,0
Exp/Cntr=0.3,0.1

Type RM Length L Ch R = 1 ,129     ,110,110,110
BEGIN DESCRIPTION:
Stream0178 0.0
END DESCRIPTION:
XS GIS Cut Line= 3
      1830696.57     13928730.64      1830819.27     13929142.21
      1831051.33     13929267.52
#Sta/Elev= 30
  4578.9 1990.95  4661.3 1985.96  4694.5 1981.54  4804.4 1971.93  4837.5 1967.21
  4844.3 1964.61  4870.7 1959.15  4903.8 1953.26  4927.8 1950.53    4937 1945.09
  4969.5 1936.65  5000.8 1923.36  5007.2 1919.03  5012.9 1917.61  5013.1 1917.11
  5016.9 1917.61  5037.6  1921.5  5044.5 1924.97  5050.2 1929.86  5060.3 1932.26
  5072.1 1937.69  5082.6  1939.3  5088.3  1942.4  5104.5 1947.54  5110.2 1950.92
  5126.4 1954.35  5132.1 1957.02  5185.4 1969.04  5219.7 1974.84  5272.1 1981.42
#Mann= 3 ,-1 , 0
  4578.9     .07       0  5012.9     .04       0  5016.9     .07       0
Bank Sta=5012.9,5016.9
XS Rating Curve= 0 ,0
Exp/Cntr=0.3,0.1

Type RM Length L Ch R = 1 ,19      ,0,0,0
BEGIN DESCRIPTION:
Stream0178 0.1
END DESCRIPTION:
XS GIS Cut Line= 4
      1830587.67     13928999.23      1830716.58     13929201.05
      1830868.92     13929271.36      1831101.01     13929311.56
#Sta/Elev= 30
  4736.2 1967.08  4759.1 1964.79  4775.2 1961.31  4796.3 1960.78  4847.9 1954.95
  4884.3 1952.21  4920.7 1940.96  4941.9 1936.58  4956.6 1930.56    4963 1926.74
  4968.9 1920.64    4981 1914.42  4981.5 1913.92  4988.8 1914.42  4999.2 1915.16
  5016.7 1918.44  5045.1 1926.14    5051 1929.31    5062 1931.85  5073.6 1936.77
  5084.1 1938.89  5106.1 1946.22    5114    1952  5119.5 1951.41  5159.8 1959.24
  5194.7 1963.94  5200.4  1966.2  5220.7 1969.81  5314.2 1980.43    5379 1990.43
#Mann= 3 ,-1 , 0
  4736.2     .07       0    4981     .04       0  4988.8     .07       0
Bank Sta=4981,4988.8
XS Rating Curve= 0 ,0
Exp/Cntr=0.3,0.1

Chan Stop Cuts=-1
Use User Specified Reach Order=0
Composite Channel Slope=5