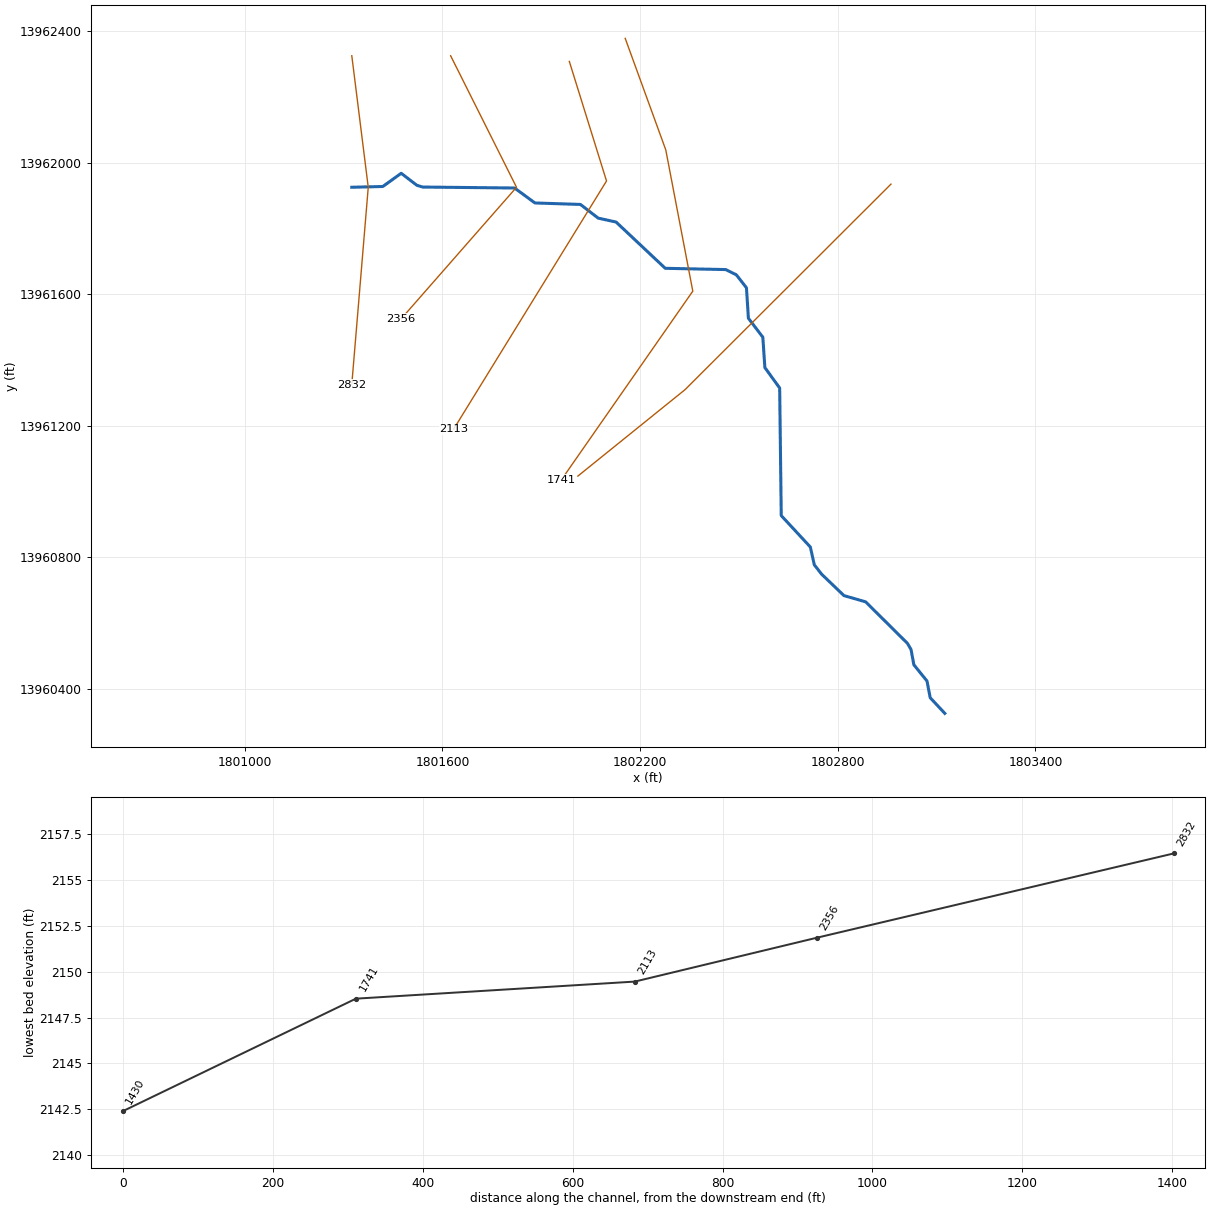
--- Stream0180.prj (project) ---

Proj Title=Stream0180 Base Level Engineering
Current Plan=p01
Default Exp/Contr=0.3,0.1
English Units
Geom File=g01
Flow File=f01
Plan File=p01
BEGIN DESCRIPTION:
Stream0180
END DESCRIPTION:

--- Stream0180.p01 (plan) ---

Plan Title=Multiple Run
Short Identifier=Multiple
Geom File=g01
Flow File=f01
Subcritical Flow
K Sum by GR= 0
Std Step Tol= 0.01
Critical Tol= 0.01
Num of Std Step Trials= 20
Max Error Tol= 0.3
Flow Tol Ratio= 0.001
Split Flow NTrial= 30
Split Flow Tol= 0.02
Split Flow Ratio= 0.02
Log Output Level= 0
Friction Slope Method= 1
Unsteady Friction Slope Method= 2
Unsteady Bridges Friction Slope Method= 1
Parabolic Critical Depth
Global Vel Dist=  1 , 1 , 1
Global Log Level= 0
CheckData=True
Encroach Param= -1, 0, 0, 0
BEGIN DESCRIPTION:
Multiple Run
END DESCRIPTION:

--- Stream0180.f01 (steady flow) ---

Flow Title=Multiple
Number of Profiles=7
Profile Names=10-year,25-year,50-year,1pct_min,100-year,1pct_plu,500-year
River Rch & RM= Stream0180,Reach-1,2832
    1225    2106    2946    1990    3970    7921    7130
Boundary for River Rch & Prof#=Stream0180,Reach-1,1
Up Type=0
Dn Type=3
Dn Slope=0.005
Boundary for River Rch & Prof#=Stream0180,Reach-1,2
Up Type=0
Dn Type=3
Dn Slope=0.005
Boundary for River Rch & Prof#=Stream0180,Reach-1,3
Up Type=0
Dn Type=3
Dn Slope=0.005
Boundary for River Rch & Prof#=Stream0180,Reach-1,4
Up Type=0
Dn Type=3
Dn Slope=0.005
Boundary for River Rch & Prof#=Stream0180,Reach-1,5
Up Type=0
Dn Type=3
Dn Slope=0.005
Boundary for River Rch & Prof#=Stream0180,Reach-1,6
Up Type=0
Dn Type=3
Dn Slope=0.005
Boundary for River Rch & Prof#=Stream0180,Reach-1,7
Up Type=0
Dn Type=3
Dn Slope=0.005

--- Stream0180.g01 (geometry) ---

Geom Title=Existing Conditions

River Reach=Stream0180,Reach-1
Reach XY= 30
      1801325.00     13961925.00      1801419.23     13961927.34
      1801474.99     13961967.49      1801522.55     13961931.02
      1801540.16     13961925.66      1801819.06     13961922.74
      1801880.94     13961877.27      1802019.07     13961872.75
      1802072.83     13961831.14      1802127.30     13961819.17
      1802276.46     13961678.54      1802459.98     13961674.68
      1802492.22     13961658.76      1802522.94     13961619.32
      1802528.86     13961526.60      1802572.65     13961469.03
      1802578.86     13961376.60      1802623.78     13961314.50
      1802628.55     13960926.47      1802716.82     13960831.04
      1802728.97     13960776.64      1802751.27     13960748.12
      1802818.93     13960683.15      1802884.68     13960664.22
      1803011.38     13960538.22      1803022.50     13960518.97
      1803031.10     13960472.81      1803070.96     13960423.33
      1803080.67     13960372.64      1803125.00     13960325.00

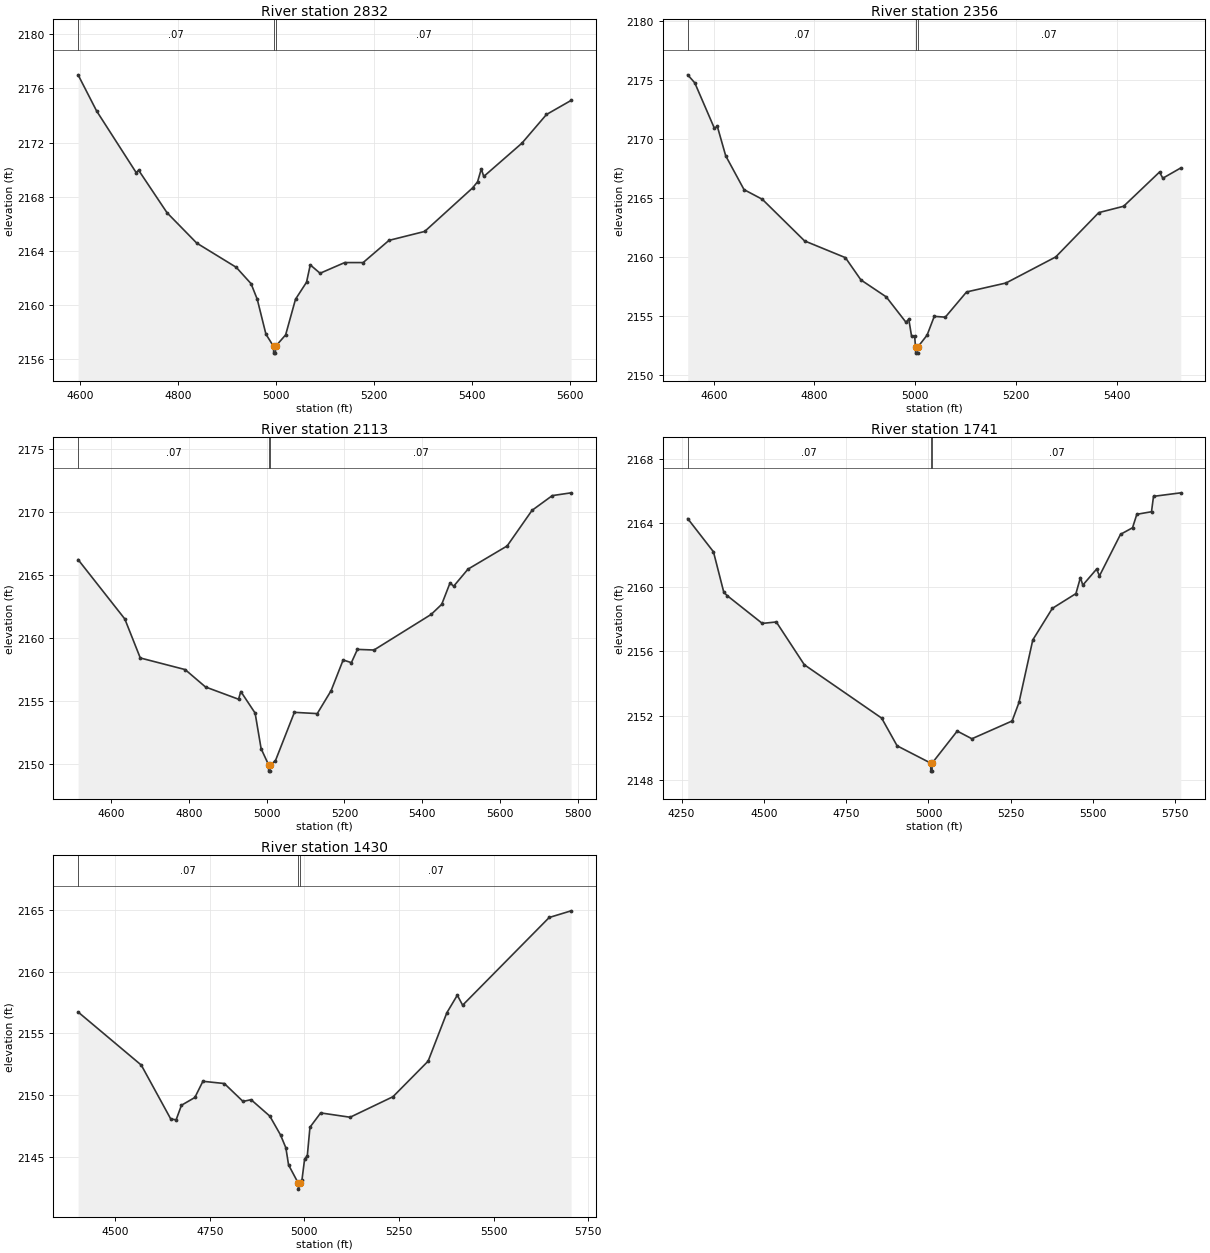
Type RM Length L Ch R = 1,2832,476,476,476
BEGIN DESCRIPTION:
Stream0180 2.0
END DESCRIPTION:
XS GIS Cut Line= 3
      1801325.00     13962325.01      1801375.00     13961925.00
      1801325.00     13961325.00
#Sta/Elev= 30
  4596.3 2177.00  4634.1 2174.33  4714.7 2169.78  4719.8 2169.95  4777.7 2166.81
  4838.2 2164.57  4918.8 2162.78  4949.0 2161.57  4961.6 2160.42  4979.3 2157.84
  4994.8 2156.94  4995.1 2156.44  4998.7 2156.44  4999.0 2156.94  5019.5 2157.79
  5039.6 2160.42  5062.1 2161.68  5069.7 2162.96  5089.7 2162.34  5139.9 2163.13
  5177.5 2163.13  5230.2 2164.77  5303.0 2165.43  5400.8 2168.65  5410.8 2169.10
  5418.4 2170.05  5423.4 2169.49  5501.2 2171.95  5551.3 2174.07  5601.5 2175.11
#Mann=3,-1,0
  4596.3    0.07       0  4994.8    0.05       0  4999.0    0.07       0
Bank Sta=4994.8,4999
Exp/Cntr=0.3,0.1

Type RM Length L Ch R = 1,2356,243,243,243
BEGIN DESCRIPTION:
Stream0180 1.0
END DESCRIPTION:
XS GIS Cut Line= 3
      1801625.01     13962324.98      1801825.00     13961925.00
      1801475.00     13961525.00
#Sta/Elev= 30
  4548.4 2175.46  4562.4 2174.78  4601.5 2170.91  4607.1 2171.10  4623.8 2168.59
  4660.2 2165.72  4696.5 2164.90  4780.4 2161.37  4861.4 2159.95  4892.2 2158.06
  4942.5 2156.62  4981.6 2154.47  4987.2 2154.73  4992.8 2153.27  4998.9 2153.27
  5000.6 2152.35  5000.9 2151.85  5004.6 2151.85  5004.8 2152.35  5023.6 2153.38
  5037.8 2154.97  5059.7 2154.90  5101.9 2157.04  5180.2 2157.80  5278.9 2160.01
  5364.3 2163.77  5413.7 2164.31  5484.9 2167.21  5491.5 2166.69  5527.1 2167.56
#Mann=3,-1,0
  4548.4    0.07       0  5000.6    0.05       0  5004.8    0.07       0
Bank Sta=5000.6,5004.8
Exp/Cntr=0.3,0.1

Type RM Length L Ch R = 1,2113,372,372,372
BEGIN DESCRIPTION:
Stream0180 0.1
END DESCRIPTION:
XS GIS Cut Line= 3
      1801985.33     13962307.65      1802098.22     13961944.10
      1801634.26     13961189.49
#Sta/Elev= 30
  4515.8 2166.23  4635.9 2161.52  4675.6 2158.43  4790.8 2157.51  4843.2 2156.13
  4928.0 2155.16  4933.9 2155.77  4970.6 2154.06  4986.0 2151.24  5005.2 2149.96
  5005.4 2149.46  5009.1 2149.46  5009.4 2149.96  5022.7 2150.28  5071.5 2154.12
  5130.2 2154.02  5165.8 2155.84  5196.7 2158.27  5217.9 2158.06  5233.4 2159.11
  5275.9 2159.06  5422.7 2161.88  5449.9 2162.68  5471.2 2164.37  5480.7 2164.12
  5517.4 2165.47  5618.0 2167.31  5681.9 2170.13  5734.0 2171.30  5782.3 2171.52
#Mann=3,-1,0
  4515.8    0.07       0  5005.2    0.05       0  5009.4    0.07       0
Bank Sta=5005.2,5009.4
Exp/Cntr=0.3,0.1

Type RM Length L Ch R = 1,1741,311,311,311
BEGIN DESCRIPTION:
Stream0180 0.0
END DESCRIPTION:
XS GIS Cut Line= 4
      1802154.89     13962377.92      1802278.07     13962038.69
      1802360.10     13961609.07      1801960.81     13961034.71
#Sta/Elev= 30
  4268.6 2164.29  4346.8 2162.22  4378.1 2159.70  4388.7 2159.48  4495.1 2157.75
  4537.7 2157.84  4622.8 2155.17  4857.7 2151.84  4904.7 2150.11  5006.8 2149.03
  5007.1 2148.53  5010.8 2148.53  5011.1 2149.03  5087.3 2151.03  5131.9 2150.55
  5254.1 2151.66  5275.0 2152.82  5316.9 2156.72  5376.3 2158.69  5447.9 2159.61
  5461.6 2160.61  5468.8 2160.14  5510.7 2161.14  5519.5 2160.72  5583.4 2163.31
  5619.9 2163.72  5632.9 2164.56  5677.5 2164.72  5683.6 2165.68  5766.4 2165.90
#Mann=3,-1,0
  4268.6    0.07       0  5006.8    0.05       0  5011.1    0.07       0
Bank Sta=5006.8,5011.1
Exp/Cntr=0.3,0.1

Type RM Length L Ch R = 1,1430,0,0,0
BEGIN DESCRIPTION:
Stream0180 T
END DESCRIPTION:
XS GIS Cut Line= 3
      1802961.66     13961934.58      1802336.70     13961309.61
      1802011.21     13961046.62
#Sta/Elev= 30
  4402.1 2156.74  4569.1 2152.44  4646.9 2148.08  4661.1 2148.01  4675.2 2149.19
  4710.6 2149.82  4731.8 2151.13  4788.4 2150.95  4837.8 2149.50  4859.1 2149.64
  4908.6 2148.31  4936.8 2146.79  4951.0 2145.74  4958.1 2144.36  4983.4 2142.90
  4983.9 2142.40  4989.3 2142.90  4993.4 2143.12  5000.5 2144.84  5007.6 2145.10
  5014.6 2147.41  5042.9 2148.57  5120.7 2148.22  5233.8 2149.88  5326.7 2152.76
  5376.2 2156.68  5403.8 2158.10  5417.9 2157.29  5646.5 2164.39  5704.4 2164.93
#Mann=3,-1,0
  4402.1    0.07       0  4983.4    0.05       0  4989.3    0.07       0
Bank Sta=4983.4,4989.3
Exp/Cntr=0.3,0.1

Chan Stop Cuts=-1