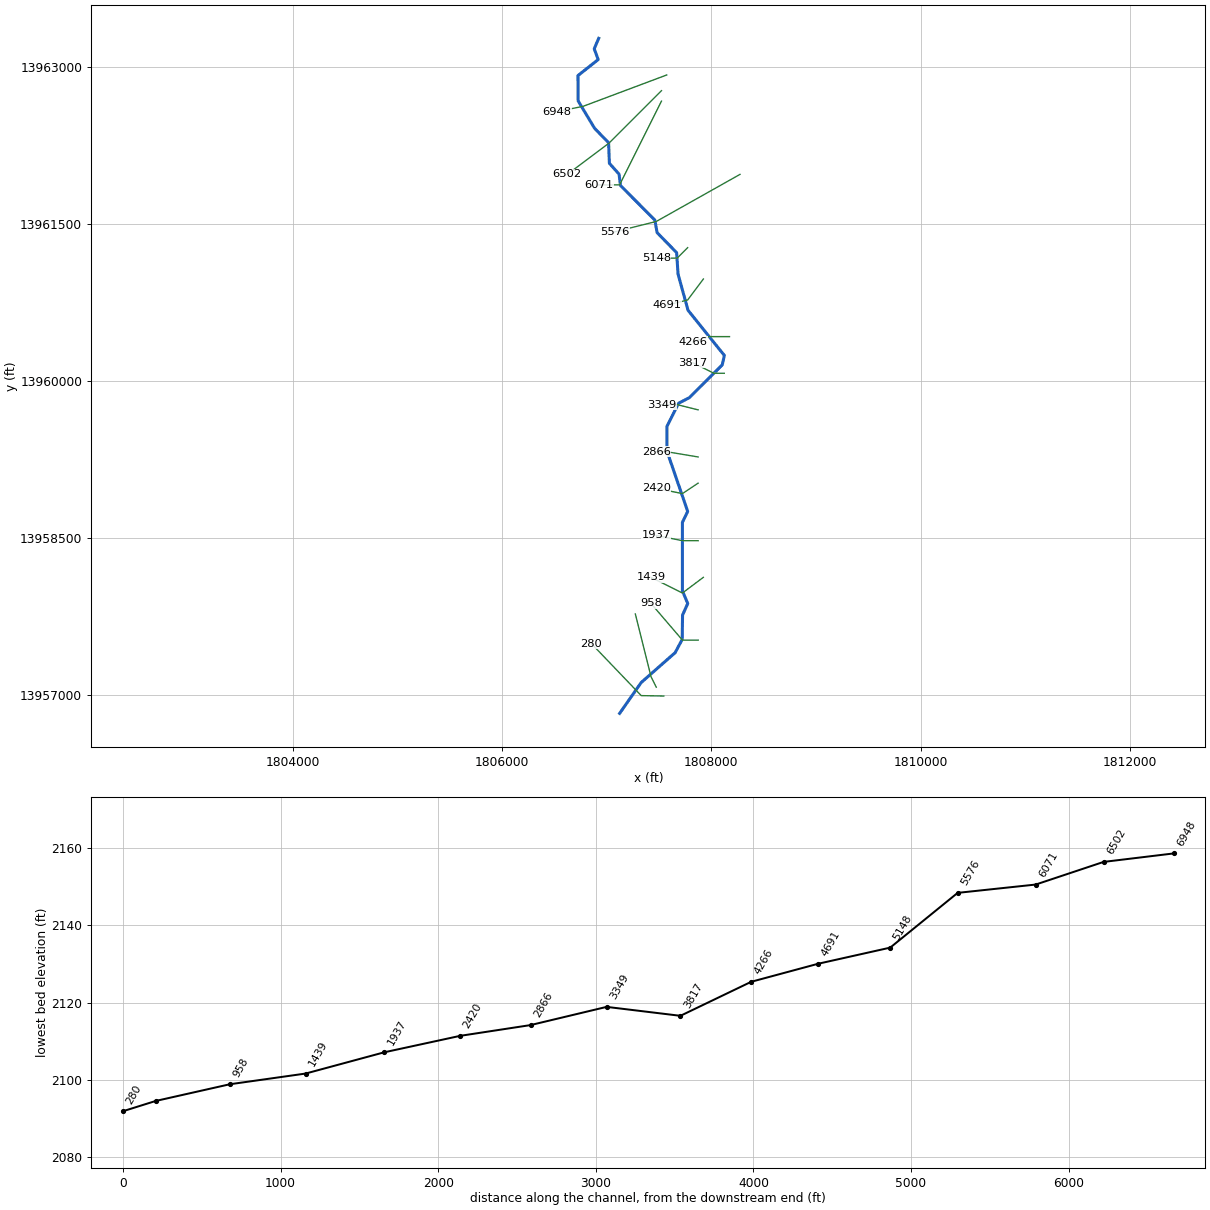
--- Stream0181.prj (project) ---

Proj Title=Stream0181 Base Level Engineering
Current Plan=p01
Default Exp/Contr=0.3,0.1
English Units
Geom File=g01
Flow File=f01
Plan File=p01
BEGIN DESCRIPTION:
Stream0181
END DESCRIPTION:

--- Stream0181.p01 (plan) ---

Plan Title=Multiple Run
Short Identifier=Multiple
Geom File=g01
Flow File=f01
Subcritical Flow
K Sum by GR= 0
Std Step Tol= 0.01
Critical Tol= 0.01
Num of Std Step Trials= 20
Max Error Tol= 0.3
Flow Tol Ratio= 0.001
Split Flow NTrial= 30
Split Flow Tol= 0.02
Split Flow Ratio= 0.02
Log Output Level= 0
Friction Slope Method= 1
Unsteady Friction Slope Method= 2
Unsteady Bridges Friction Slope Method= 1
Parabolic Critical Depth
Global Vel Dist=  1 , 1 , 1
Global Log Level= 0
CheckData=True
Encroach Param= -1, 0, 0, 0
BEGIN DESCRIPTION:
Multiple Run
END DESCRIPTION:

--- Stream0181.f01 (steady flow) ---

Flow Title=Multiple
Number of Profiles=7
Profile Names=10-year,25-year,50-year,1pct_min,100-year,1pct_plu,500-year
River Rch & RM= Stream0181,Reach-1,6948
    1749    3053    4314    2937    5860   11693   10705
Boundary for River Rch & Prof#=Stream0181,Reach-1,1
Up Type=0
Dn Type=3
Dn Slope=0.005
Boundary for River Rch & Prof#=Stream0181,Reach-1,2
Up Type=0
Dn Type=3
Dn Slope=0.005
Boundary for River Rch & Prof#=Stream0181,Reach-1,3
Up Type=0
Dn Type=3
Dn Slope=0.005
Boundary for River Rch & Prof#=Stream0181,Reach-1,4
Up Type=0
Dn Type=3
Dn Slope=0.005
Boundary for River Rch & Prof#=Stream0181,Reach-1,5
Up Type=0
Dn Type=3
Dn Slope=0.005
Boundary for River Rch & Prof#=Stream0181,Reach-1,6
Up Type=0
Dn Type=3
Dn Slope=0.005
Boundary for River Rch & Prof#=Stream0181,Reach-1,7
Up Type=0
Dn Type=3
Dn Slope=0.005

--- Stream0181.g01 (geometry) ---

Geom Title=Existing Conditions

River Reach=Stream0181,Reach-1
Reach XY= 30
      1806925.00     13963275.00      1806882.35     13963175.03
      1806919.99     13963072.46      1806727.05     13962919.16
      1806728.75     13962676.55      1806885.78     13962415.32
      1807019.54     13962277.45      1807027.07     13962080.86
      1807119.46     13961977.42      1807132.86     13961868.83
      1807461.60     13961538.30      1807482.86     13961418.83
      1807669.48     13961227.43      1807683.28     13961021.78
      1807778.61     13960676.50      1808125.68     13960245.08
      1808105.42     13960154.85      1807791.66     13959841.66
      1807688.47     13959788.57      1807576.20     13959564.50
      1807577.26     13959330.94      1807775.28     13958754.82
      1807724.81     13958650.09      1807725.07     13957995.03
      1807775.82     13957875.00      1807726.22     13957764.50
      1807722.76     13957530.93      1807655.22     13957404.91
      1807330.62     13957119.38      1807125.00     13956825.00

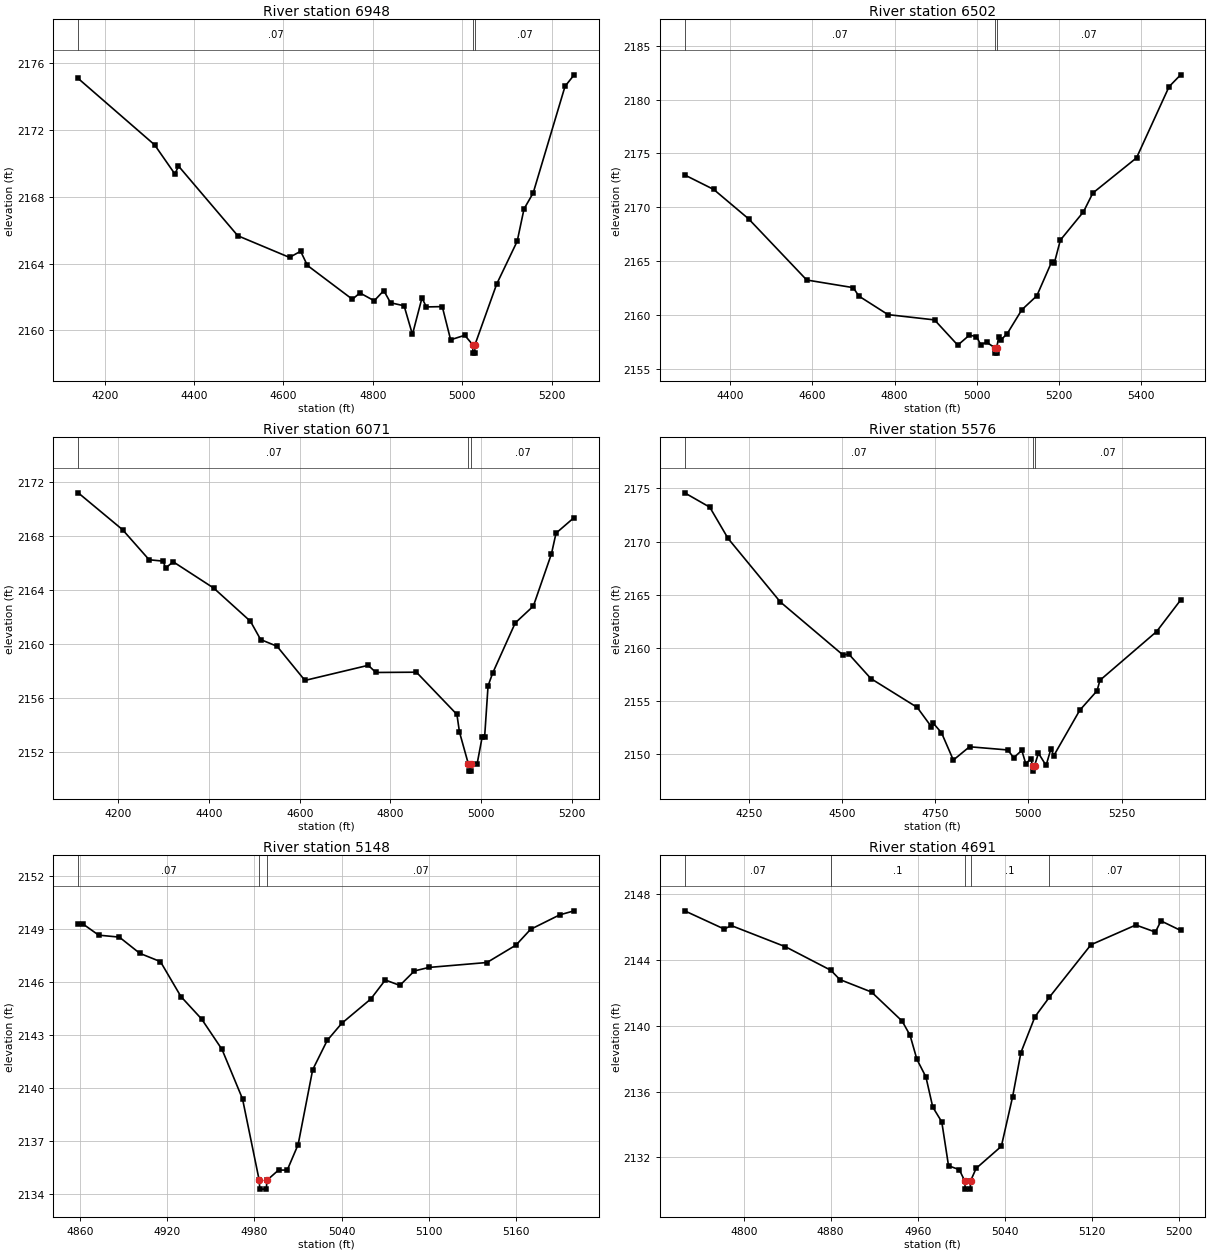
Type RM Length L Ch R = 1,6948,446,446,446
BEGIN DESCRIPTION:
Stream0181 15.0
END DESCRIPTION:
XS GIS Cut Line= 3
      1807574.99     13962924.99      1806775.00     13962625.00
      1806525.03     13962575.01
#Sta/Elev= 30
  4140.9 2175.10  4311.8 2171.12  4357.2 2169.37  4365.2 2169.85  4497.8 2165.67
  4613.5 2164.37  4638.4 2164.74  4653.5 2163.89  4754.1 2161.86  4771.0 2162.24
  4803.0 2161.77  4824.4 2162.38  4839.5 2161.65  4869.8 2161.47  4888.5 2159.75
  4909.8 2161.94  4919.6 2161.40  4955.2 2161.42  4973.9 2159.43  5005.5 2159.70
  5023.4 2159.13  5023.8 2158.63  5027.9 2158.63  5028.3 2159.13  5076.9 2162.77
  5122.8 2165.34  5138.1 2167.28  5158.5 2168.23  5229.8 2174.63  5250.2 2175.32
#Mann=3,-1,0
  4140.9    0.07       0  5023.4    0.05       0  5028.3    0.07       0
Bank Sta=5023.4,5028.3
Exp/Cntr=0.3,0.1

Type RM Length L Ch R = 1,6502,431,431,431
BEGIN DESCRIPTION:
Stream0181 14.0
END DESCRIPTION:
XS GIS Cut Line= 3
      1807524.98     13962774.98      1807025.00     13962275.00
      1806624.98     13961974.99
#Sta/Elev= 30
  4288.9 2173.00  4359.6 2171.65  4444.4 2168.92  4585.9 2163.23  4699.0 2162.52
  4713.1 2161.73  4783.8 2160.01  4897.0 2159.52  4953.6 2157.17  4981.8 2158.10
  4999.1 2157.97  5009.5 2157.22  5024.1 2157.44  5043.5 2156.93  5043.9 2156.43
  5048.1 2156.43  5048.4 2156.93  5053.3 2157.95  5059.5 2157.69  5074.1 2158.25
  5109.5 2160.46  5146.0 2161.76  5182.4 2164.94  5188.7 2164.82  5203.3 2166.94
  5259.5 2169.57  5282.4 2171.32  5388.7 2174.59  5467.9 2181.21  5496.0 2182.31
#Mann=3,-1,0
  4288.9    0.07       0  5043.5    0.05       0  5048.4    0.07       0
Bank Sta=5043.5,5048.4
Exp/Cntr=0.3,0.1

Type RM Length L Ch R = 1,6071,495,495,495
BEGIN DESCRIPTION:
Stream0181 13.0
END DESCRIPTION:
XS GIS Cut Line= 3
      1807525.00     13962675.00      1807125.00     13961875.00
      1806925.02     13961875.00
#Sta/Elev= 30
  4111.1 2171.19  4208.9 2168.46  4267.6 2166.23  4298.4 2166.13  4304.0 2165.62
  4320.7 2166.08  4410.2 2164.13  4491.2 2161.67  4513.6 2160.32  4549.9 2159.82
  4611.4 2157.29  4751.2 2158.41  4767.9 2157.88  4857.4 2157.90  4946.8 2154.77
  4952.4 2153.47  4972.3 2151.07  4972.7 2150.57  4976.9 2150.57  4977.2 2151.07
  4991.5 2151.13  5002.7 2153.13  5008.0 2153.13  5015.5 2156.88  5025.5 2157.82
  5075.5 2161.55  5115.5 2162.80  5155.5 2166.68  5165.5 2168.20  5205.5 2169.36
#Mann=3,-1,0
  4111.1    0.07       0  4972.3    0.05       0  4977.2    0.07       0
Bank Sta=4972.3,4977.2
Exp/Cntr=0.3,0.1

Type RM Length L Ch R = 1,5576,428,428,428
BEGIN DESCRIPTION:
Stream0181 12.0
END DESCRIPTION:
XS GIS Cut Line= 3
      1808275.03     13961975.02      1807475.00     13961525.00
      1807075.02     13961425.00
#Sta/Elev= 30
  4078.1 2174.58  4145.4 2173.23  4194.5 2170.29  4334.7 2164.32  4502.6 2159.34
  4518.3 2159.42  4577.5 2157.12  4701.8 2154.41  4739.4 2152.61  4745.2 2152.91
  4766.9 2152.03  4798.7 2149.46  4842.1 2150.71  4944.7 2150.41  4960.6 2149.68
  4982.3 2150.37  4993.1 2149.10  5006.3 2149.60  5011.5 2148.92  5011.9 2148.42
  5016.5 2148.92  5026.9 2150.11  5047.5 2148.95  5060.4 2150.52  5068.2 2149.88
  5137.7 2154.14  5184.1 2155.97  5191.9 2156.96  5343.9 2161.54  5408.3 2164.50
#Mann=3,-1,0
  4078.1    0.07       0  5011.5    0.05       0  5016.5    0.07       0
Bank Sta=5011.5,5016.5
Exp/Cntr=0.3,0.1

Type RM Length L Ch R = 1,5148,457,457,457
BEGIN DESCRIPTION:
Stream0181 11.0
END DESCRIPTION:
XS GIS Cut Line= 3
      1807775.00     13961275.00      1807675.00     13961175.00
      1807475.02     13961175.00
#Sta/Elev= 30
  4858.7 2149.27  4862.2 2149.27  4872.8 2148.65  4887.0 2148.54  4901.1 2147.62
  4915.3 2147.15  4929.4 2145.17  4943.6 2143.90  4957.7 2142.17  4971.8 2139.37
  4983.3 2134.75  4983.7 2134.25  4988.2 2134.25  4988.6 2134.75  4996.6 2135.33
  5002.6 2135.33  5010.1 2136.78  5020.1 2141.02  5030.1 2142.68  5040.1 2143.65
  5060.1 2145.03  5070.1 2146.11  5080.1 2145.80  5090.1 2146.62  5100.1 2146.82
  5140.1 2147.10  5160.1 2148.09  5170.1 2148.98  5190.1 2149.80  5200.1 2150.03
#Mann=3,-1,0
  4858.7    0.07       0  4983.3    0.05       0  4988.6    0.07       0
Bank Sta=4983.3,4988.6
Exp/Cntr=0.3,0.1

Type RM Length L Ch R = 1,4691,425,425,425
BEGIN DESCRIPTION:
Stream0181 10.0
END DESCRIPTION:
XS GIS Cut Line= 3
      1807925.02     13960975.03      1807775.00     13960775.00
      1807574.99     13960725.00
#Sta/Elev= 30
  4745.7 2146.97  4782.2 2145.86  4788.4 2146.08  4838.4 2144.79  4880.2 2143.36
  4888.4 2142.80  4917.6 2142.04  4945.7 2140.28  4953.0 2139.42  4959.3 2137.96
  4967.6 2136.89  4973.9 2135.06  4982.2 2134.16  4988.4 2131.50  4998.3 2131.26
  5003.3 2130.58  5003.8 2130.08  5008.3 2130.08  5008.7 2130.58  5013.8 2131.34
  5037.0 2132.68  5047.3 2135.67  5055.0 2138.37  5067.9 2140.54  5081.1 2141.72
  5119.4 2144.91  5160.7 2146.11  5178.7 2145.68  5183.8 2146.36  5201.9 2145.78
#Mann=5,-1,0
  4745.7    0.07       0  4880.2     0.1       0  5003.3    0.05       0
  5008.7     0.1       0  5081.1    0.07       0
Bank Sta=5003.3,5008.7
Exp/Cntr=0.3,0.1

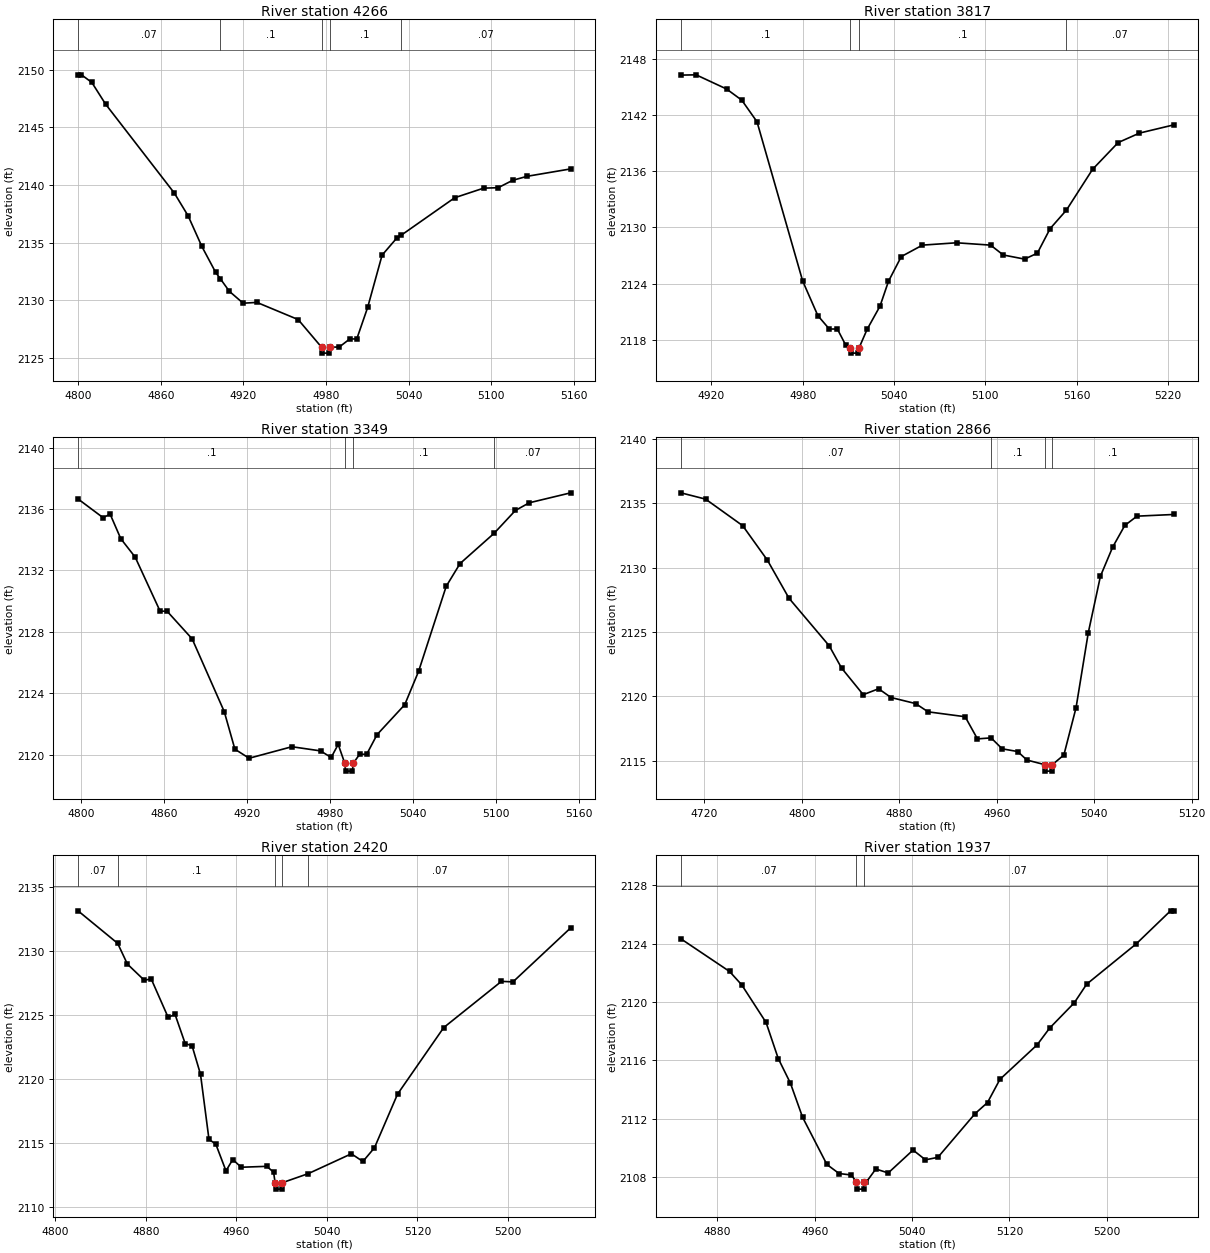
Type RM Length L Ch R = 1,4266,449,449,449
BEGIN DESCRIPTION:
Stream0181 9.0
END DESCRIPTION:
XS GIS Cut Line= 3
      1808174.97     13960425.00      1807975.00     13960425.00
      1807824.98     13960374.99
#Sta/Elev= 30
  4799.8 2149.55  4802.3 2149.55  4809.8 2148.89  4819.8 2147.01  4869.8 2139.29
  4879.8 2137.32  4889.8 2134.66  4899.8 2132.42  4903.1 2131.88  4909.8 2130.77
  4919.8 2129.74  4929.8 2129.81  4959.8 2128.32  4976.9 2125.91  4977.4 2125.41
  4982.2 2125.41  4982.6 2125.91  4989.8 2125.95  4997.3 2126.64  5002.4 2126.64
  5010.3 2129.37  5020.8 2133.91  5031.4 2135.38  5034.5 2135.62  5073.6 2138.89
  5094.6 2139.72  5105.2 2139.76  5115.7 2140.40  5126.3 2140.75  5157.9 2141.39
#Mann=5,-1,0
  4799.8    0.07       0  4903.1     0.1       0  4976.9    0.05       0
  4982.6     0.1       0  5034.5    0.07       0
Bank Sta=4976.9,4982.6
Exp/Cntr=0.3,0.1

Type RM Length L Ch R = 1,3817,468,468,468
BEGIN DESCRIPTION:
Stream0181 8.0
END DESCRIPTION:
XS GIS Cut Line= 3
      1808125.05     13960075.00      1808025.00     13960075.00
      1807824.96     13960175.02
#Sta/Elev= 30
  4900.0 2146.24  4910.0 2146.27  4930.0 2144.76  4940.0 2143.57  4950.0 2141.27
  4980.0 2124.30  4990.0 2120.60  4997.5 2119.18  5002.8 2119.18  5008.4 2117.43
  5011.1 2117.11  5011.6 2116.61  5016.4 2116.61  5016.9 2117.11  5022.4 2119.16
  5030.8 2121.61  5036.4 2124.27  5044.8 2126.90  5058.7 2128.12  5081.1 2128.37
  5103.5 2128.12  5111.8 2127.07  5125.8 2126.63  5134.2 2127.26  5142.6 2129.88
  5153.3 2131.85  5170.5 2136.20  5187.3 2139.05  5201.3 2140.06  5223.7 2140.93
#Mann=4,-1,0
  4900.0     0.1       0  5011.1    0.05       0  5016.9     0.1       0
  5153.3    0.07       0
Bank Sta=5011.1,5016.9
Exp/Cntr=0.3,0.1

Type RM Length L Ch R = 1,3349,483,483,483
BEGIN DESCRIPTION:
Stream0181 7.0
END DESCRIPTION:
XS GIS Cut Line= 3
      1807875.02     13959725.00      1807675.00     13959775.00
      1807524.98     13959775.00
#Sta/Elev= 30
  4798.0 2136.66  4816.1 2135.44  4821.2 2135.67  4828.9 2134.07  4839.3 2132.87
  4857.3 2129.35  4862.4 2129.34  4880.5 2127.54  4903.7 2122.80  4911.4 2120.35
  4921.7 2119.76  4952.6 2120.51  4973.3 2120.24  4981.0 2119.81  4986.1 2120.66
  4990.9 2119.42  4991.4 2118.92  4996.4 2118.92  4996.9 2119.42  5001.6 2120.02
  5006.7 2120.02  5014.2 2121.30  5034.2 2123.25  5044.2 2125.42  5064.2 2130.97
  5074.2 2132.45  5098.8 2134.42  5114.2 2135.91  5124.2 2136.41  5154.2 2137.06
#Mann=4,-1,0
  4798.0     0.1       0  4990.9    0.05       0  4996.9     0.1       0
  5098.8    0.07       0
Bank Sta=4990.9,4996.9
Exp/Cntr=0.3,0.1

Type RM Length L Ch R = 1,2866,446,446,446
BEGIN DESCRIPTION:
Stream0181 6.0
END DESCRIPTION:
XS GIS Cut Line= 3
      1807875.02     13959275.00      1807575.00     13959325.00
      1807474.95     13959325.00
#Sta/Elev= 30
  4700.9 2135.80  4721.2 2135.31  4751.6 2133.25  4771.9 2130.57  4789.6 2127.62
  4822.6 2123.93  4832.7 2122.21  4850.5 2120.14  4863.1 2120.60  4873.3 2119.92
  4893.5 2119.45  4903.7 2118.81  4934.1 2118.43  4944.2 2116.71  4955.4 2116.79
  4964.5 2115.94  4977.2 2115.73  4984.8 2115.07  4999.5 2114.71  5000.0 2114.21
  5005.1 2114.21  5005.6 2114.71  5015.1 2115.46  5025.1 2119.13  5035.1 2124.93
  5045.1 2129.33  5055.1 2131.58  5065.1 2133.27  5075.1 2133.99  5105.1 2134.12
#Mann=4,-1,0
  4700.9    0.07       0  4955.4     0.1       0  4999.5    0.05       0
  5005.6     0.1       0
Bank Sta=4999.5,5005.6
Exp/Cntr=0.3,0.1

Type RM Length L Ch R = 1,2420,483,483,483
BEGIN DESCRIPTION:
Stream0181 5.0
END DESCRIPTION:
XS GIS Cut Line= 3
      1807875.02     13959025.01      1807725.00     13958925.00
      1807474.95     13958975.01
#Sta/Elev= 30
  4820.1 2133.17  4855.1 2130.63  4863.7 2129.01  4878.7 2127.74  4884.7 2127.86
  4899.7 2124.85  4905.8 2125.08  4914.8 2122.79  4920.8 2122.64  4928.3 2120.40
  4935.8 2115.31  4941.8 2114.95  4950.8 2112.86  4956.8 2113.74  4964.3 2113.14
  4986.9 2113.21  4992.9 2112.75  4994.2 2111.93  4994.7 2111.43  5000.0 2111.43
  5000.5 2111.93  5023.5 2112.64  5061.6 2114.19  5071.8 2113.59  5082.0 2114.66
  5102.4 2118.85  5143.2 2124.05  5194.2 2127.66  5204.4 2127.62  5255.4 2131.84
#Mann=5,-1,0
  4820.1    0.07       0  4855.1     0.1       0  4994.2    0.05       0
  5000.5     0.1       0  5023.5    0.07       0
Bank Sta=4994.2,5000.5
Exp/Cntr=0.3,0.1

Type RM Length L Ch R = 1,1937,498,498,498
BEGIN DESCRIPTION:
Stream0181 4.0
END DESCRIPTION:
XS GIS Cut Line= 3
      1807874.98     13958475.00      1807725.00     13958475.00
      1807475.03     13958524.99
#Sta/Elev= 30
  4850.0 2124.33  4890.0 2122.09  4900.0 2121.17  4920.0 2118.59  4930.0 2116.12
  4940.0 2114.43  4950.0 2112.09  4970.0 2108.85  4980.0 2108.23  4990.0 2108.13
  4994.3 2107.66  4994.8 2107.16  5000.2 2107.16  5000.7 2107.66  5002.5 2107.66
  5010.2 2108.54  5020.4 2108.27  5040.8 2109.84  5051.0 2109.17  5061.2 2109.34
  5091.8 2112.34  5102.0 2113.10  5112.2 2114.69  5142.8 2117.06  5153.0 2118.20
  5173.3 2119.94  5183.5 2121.22  5224.3 2123.99  5252.4 2126.25  5254.9 2126.25
#Mann=3,-1,0
  4850.0    0.07       0  4994.3    0.05       0  5000.7    0.07       0
Bank Sta=4994.3,5000.7
Exp/Cntr=0.3,0.1

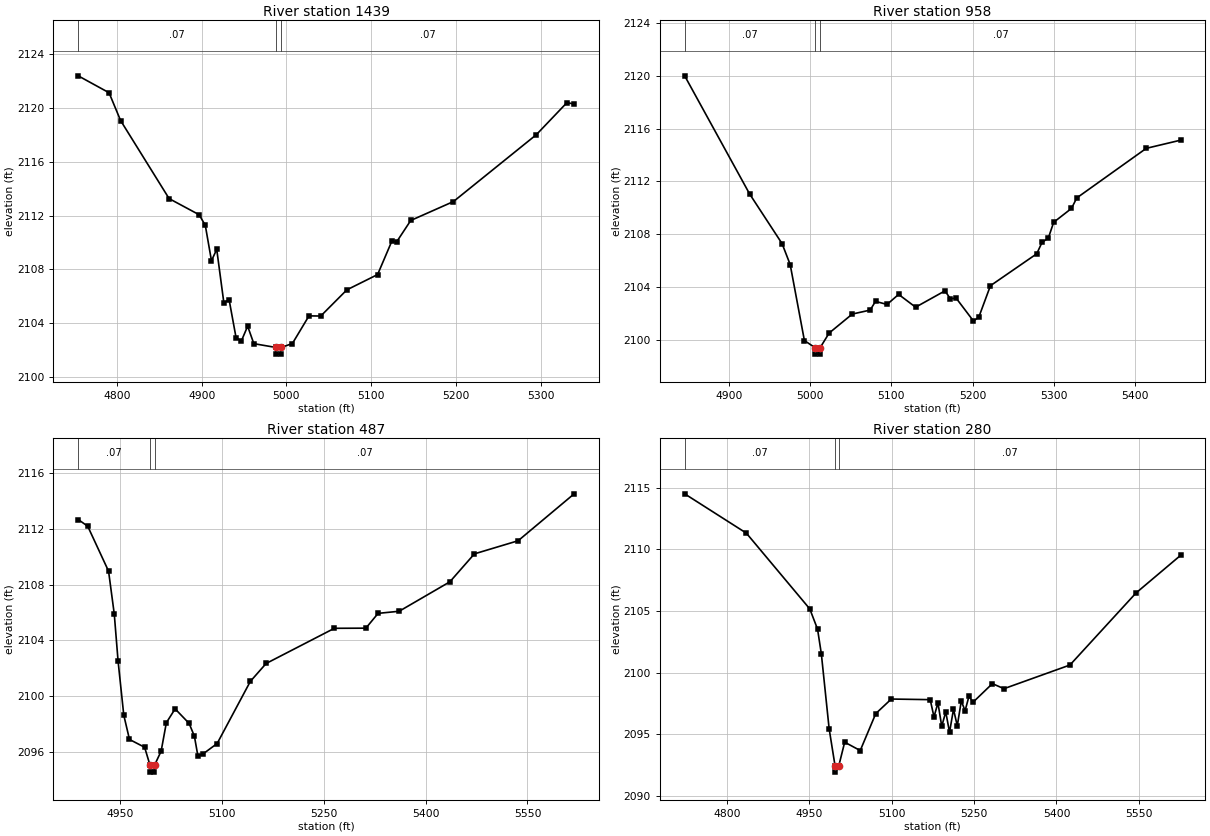
Type RM Length L Ch R = 1,1439,481,481,481
BEGIN DESCRIPTION:
Stream0181 3.0
END DESCRIPTION:
XS GIS Cut Line= 3
      1807924.99     13958124.99      1807725.00     13957975.00
      1807425.00     13958125.00
#Sta/Elev= 30
  4754.3 2122.41  4790.7 2121.15  4804.3 2119.08  4861.6 2113.26  4897.0 2112.06
  4904.3 2111.27  4911.6 2108.63  4917.8 2109.48  4926.2 2105.50  4932.4 2105.73
  4940.7 2102.87  4947.0 2102.67  4954.3 2103.75  4961.6 2102.45  4987.4 2102.17
  4987.9 2101.67  4993.5 2101.67  4994.0 2102.17  5007.1 2102.46  5026.7 2104.52
  5040.6 2104.51  5071.4 2106.46  5107.7 2107.60  5124.5 2110.09  5130.1 2110.03
  5146.8 2111.63  5197.2 2113.04  5295.0 2118.02  5331.3 2120.42  5339.7 2120.30
#Mann=3,-1,0
  4754.3    0.07       0  4987.4    0.05       0  4994.0    0.07       0
Bank Sta=4987.4,4994
Exp/Cntr=0.3,0.1

Type RM Length L Ch R = 1,958,471,471,471
BEGIN DESCRIPTION:
Stream0181 2.0
END DESCRIPTION:
XS GIS Cut Line= 3
      1807875.01     13957525.00      1807725.00     13957525.00
      1807424.99     13957875.01
#Sta/Elev= 30
  4845.3 2120.01  4925.3 2111.05  4965.3 2107.28  4975.3 2105.69  4992.8 2099.93
  5005.7 2099.40  5006.2 2098.90  5011.8 2098.90  5012.3 2099.40  5023.3 2100.50
  5051.8 2101.94  5073.8 2102.24  5080.4 2102.90  5094.6 2102.67  5108.9 2103.43
  5129.8 2102.46  5166.0 2103.70  5172.6 2103.10  5179.7 2103.15  5201.1 2101.41
  5207.7 2101.71  5222.0 2104.09  5279.0 2106.51  5285.6 2107.38  5293.3 2107.70
  5299.9 2108.90  5321.8 2109.95  5328.4 2110.75  5414.0 2114.51  5456.3 2115.13
#Mann=3,-1,0
  4845.3    0.07       0  5005.7    0.05       0  5012.3    0.07       0
Bank Sta=5005.7,5012.3
Exp/Cntr=0.3,0.1

Type RM Length L Ch R = 1,487,207,207,207
BEGIN DESCRIPTION:
Stream0181 1.0
END DESCRIPTION:
XS GIS Cut Line= 3
      1807475.00     13957075.00      1807425.00     13957175.00
      1807274.99     13957775.03
#Sta/Elev= 30
  4888.4 2112.66  4902.4 2112.18  4933.1 2108.96  4941.5 2105.89  4947.1 2102.52
  4955.5 2098.65  4963.9 2096.91  4986.2 2096.35  4994.1 2095.07  4994.6 2094.57
  5000.3 2094.57  5000.8 2095.07  5010.5 2096.07  5018.2 2098.11  5031.1 2099.10
  5051.7 2098.06  5059.5 2097.14  5064.6 2095.74  5072.4 2095.88  5093.0 2096.62
  5141.9 2101.07  5165.1 2102.35  5265.6 2104.87  5312.0 2104.88  5330.0 2105.94
  5361.0 2106.09  5435.7 2108.20  5471.8 2110.20  5536.2 2111.14  5618.7 2114.50
#Mann=3,-1,0
  4888.4    0.07       0  4994.1    0.05       0  5000.8    0.07       0
Bank Sta=4994.1,5000.8
Exp/Cntr=0.3,0.1

Type RM Length L Ch R = 1,280,0,0,0
BEGIN DESCRIPTION:
Stream0181 0.0
END DESCRIPTION:
XS GIS Cut Line= 3
      1807547.26     13956990.73      1807331.33     13956994.79
      1806856.14     13957490.84
#Sta/Elev= 30
  4723.1 2114.50  4835.4 2111.31  4950.9 2105.16  4965.0 2103.52  4971.9 2101.52
  4986.1 2095.44  4996.9 2092.42  4997.4 2091.92  5003.6 2092.42  5014.4 2094.35
  5042.7 2093.67  5071.0 2096.67  5099.3 2097.85  5170.1 2097.80  5177.0 2096.40
  5184.2 2097.54  5191.1 2095.64  5198.4 2096.81  5205.3 2095.15  5212.5 2097.02
  5219.4 2095.68  5226.7 2097.69  5233.6 2096.90  5240.8 2098.10  5247.8 2097.58
  5283.3 2099.10  5304.4 2098.69  5424.5 2100.61  5544.9 2106.46  5626.0 2109.51
#Mann=3,-1,0
  4723.1    0.07       0  4996.9    0.05       0  5003.6    0.07       0
Bank Sta=4996.9,5003.6
Exp/Cntr=0.3,0.1

Chan Stop Cuts=-1