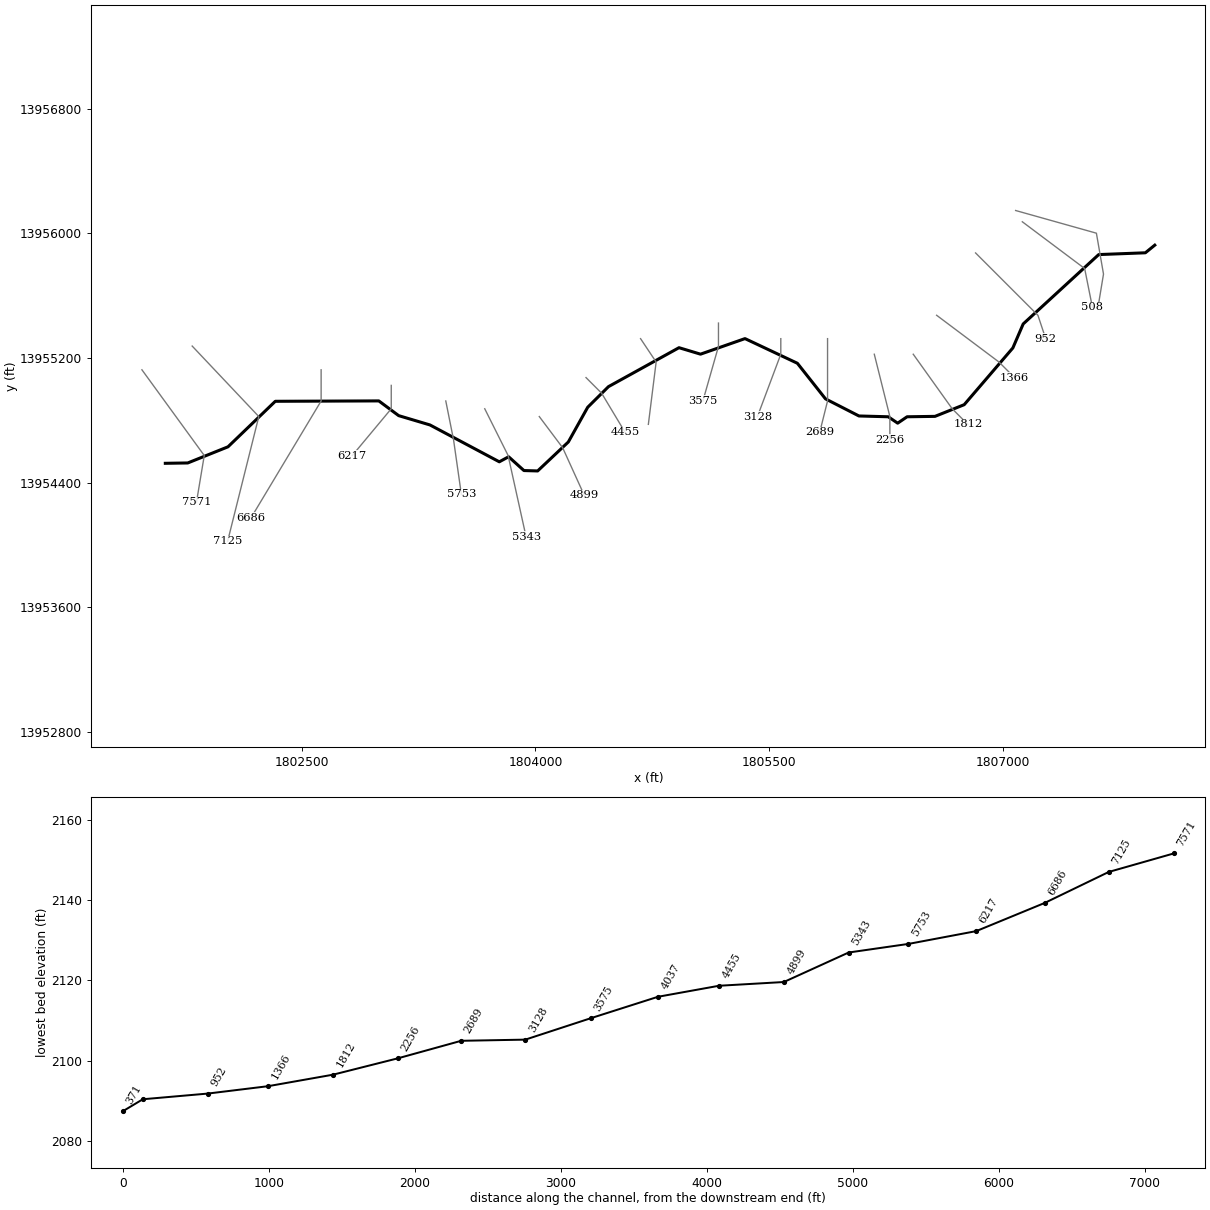
--- Stream0182.prj (project) ---

Proj Title=Stream0182 Base Level Engineering
Current Plan=p01
Default Exp/Contr=0.3,0.1
English Units
Geom File=g01
Flow File=f01
Plan File=p01
BEGIN DESCRIPTION:
Stream0182
END DESCRIPTION:

--- Stream0182.p01 (plan) ---

Plan Title=Multiple Run
Short Identifier=Multiple
Geom File=g01
Flow File=f01
Subcritical Flow
K Sum by GR= 0
Std Step Tol= 0.01
Critical Tol= 0.01
Num of Std Step Trials= 20
Max Error Tol= 0.3
Flow Tol Ratio= 0.001
Split Flow NTrial= 30
Split Flow Tol= 0.02
Split Flow Ratio= 0.02
Log Output Level= 0
Friction Slope Method= 1
Unsteady Friction Slope Method= 2
Unsteady Bridges Friction Slope Method= 1
Parabolic Critical Depth
Global Vel Dist=  1 , 1 , 1
Global Log Level= 0
CheckData=True
Encroach Param= -1, 0, 0, 0
BEGIN DESCRIPTION:
Multiple Run
END DESCRIPTION:

--- Stream0182.f01 (steady flow) ---

Flow Title=Multiple
Number of Profiles=7
Profile Names=10-year,25-year,50-year,1pct_min,100-year,1pct_plu,500-year
River Rch & RM= Stream0182,Reach-1,7571
    1672    2917    4120    2805    5596   11166   10222
Boundary for River Rch & Prof#=Stream0182,Reach-1,1
Up Type=0
Dn Type=3
Dn Slope=0.005
Boundary for River Rch & Prof#=Stream0182,Reach-1,2
Up Type=0
Dn Type=3
Dn Slope=0.005
Boundary for River Rch & Prof#=Stream0182,Reach-1,3
Up Type=0
Dn Type=3
Dn Slope=0.005
Boundary for River Rch & Prof#=Stream0182,Reach-1,4
Up Type=0
Dn Type=3
Dn Slope=0.005
Boundary for River Rch & Prof#=Stream0182,Reach-1,5
Up Type=0
Dn Type=3
Dn Slope=0.005
Boundary for River Rch & Prof#=Stream0182,Reach-1,6
Up Type=0
Dn Type=3
Dn Slope=0.005
Boundary for River Rch & Prof#=Stream0182,Reach-1,7
Up Type=0
Dn Type=3
Dn Slope=0.005

--- Stream0182.g01 (geometry) ---

Geom Title=Existing Conditions

River Reach=Stream0182,Reach-1
Reach XY= 30
      1801625.00     13954525.00      1801769.08     13954527.22
      1802027.30     13954630.83      1802330.85     13954922.94
      1802995.18     13954925.43      1803122.71     13954830.85
      1803323.42     13954771.17      1803768.45     13954534.59
      1803828.33     13954566.99      1803926.50     13954478.48
      1804014.52     13954475.93      1804211.37     13954661.79
      1804335.78     13954884.68      1804468.94     13955016.86
      1804921.68     13955266.95      1805059.72     13955225.39
      1805345.18     13955325.29      1805681.34     13955166.98
      1805861.78     13954938.62      1806076.55     13954828.75
      1806264.56     13954823.62      1806325.00     13954782.56
      1806385.44     13954823.62      1806564.50     13954826.22
      1806751.93     13954901.15      1807064.23     13955265.32
      1807130.59     13955419.39      1807615.20     13955864.52
      1807914.60     13955875.96      1807975.00     13955925.00

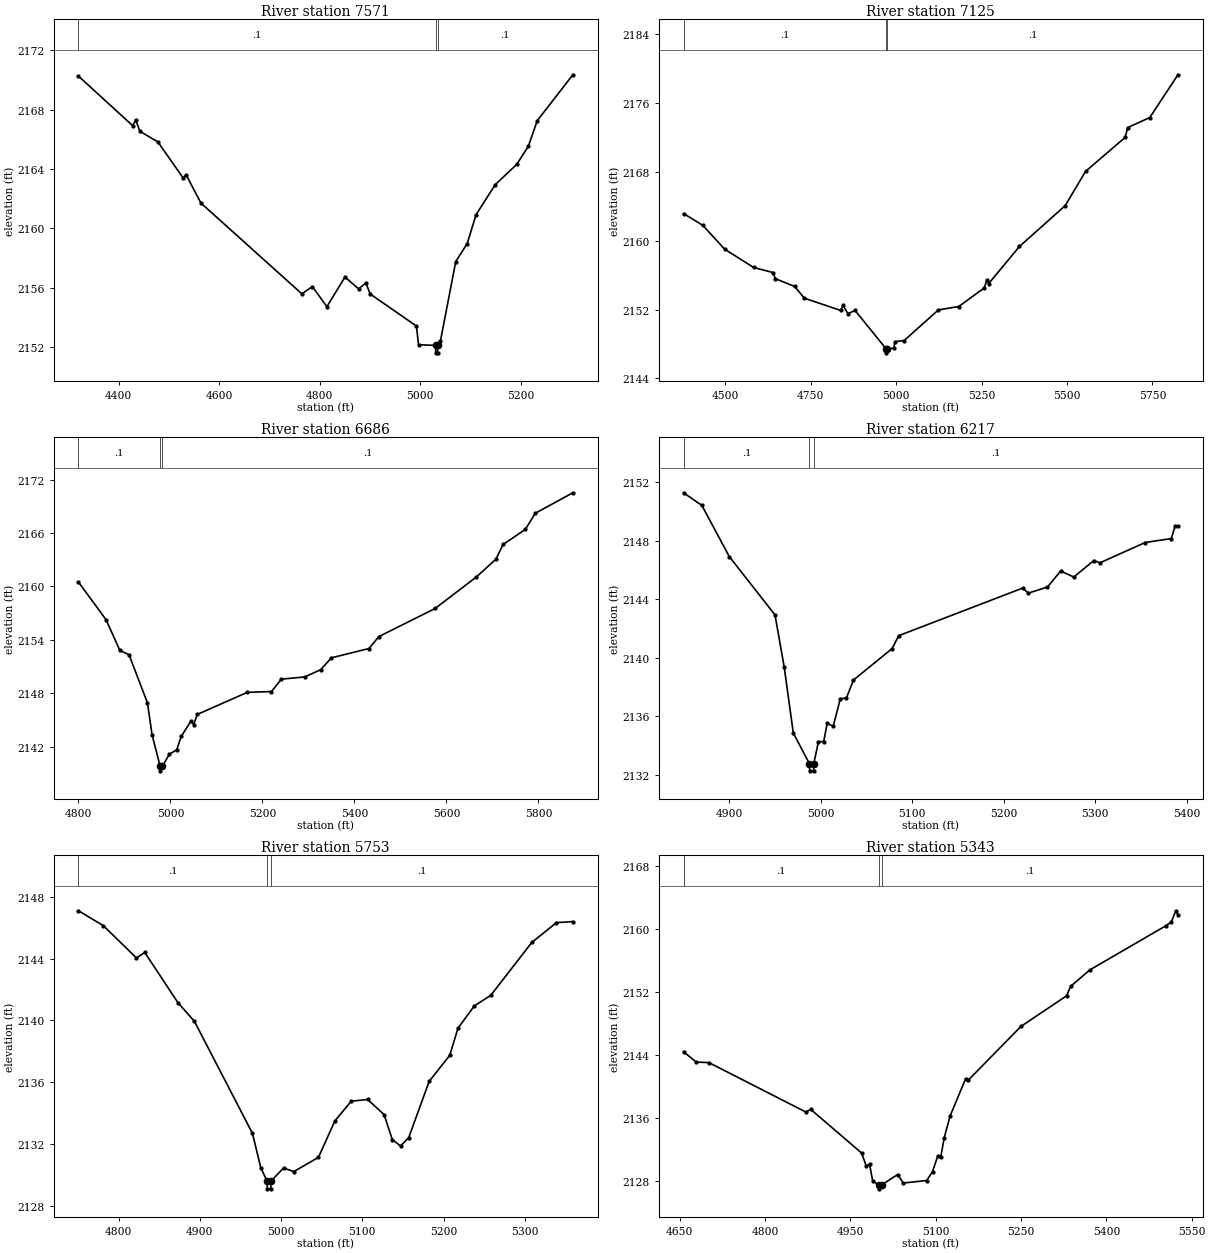
Type RM Length L Ch R = 1,7571,446,446,446
BEGIN DESCRIPTION:
Stream0182 17.0
END DESCRIPTION:
XS GIS Cut Line= 3
      1801474.99     13955125.02      1801875.00     13954575.00
      1801825.01     13954275.03
#Sta/Elev= 30
  4319.9 2170.27  4427.7 2166.93  4433.9 2167.29  4442.4 2166.54  4478.0 2165.83
  4528.2 2163.40  4534.4 2163.60  4563.7 2161.70  4764.7 2155.57  4785.5 2156.06
  4814.5 2154.71  4850.5 2156.71  4877.5 2155.91  4892.2 2156.30  4900.7 2155.56
  4992.7 2153.40  4996.9 2152.14  5030.8 2152.09  5031.1 2151.59  5034.8 2151.59
  5035.0 2152.09  5040.5 2152.39  5071.0 2157.75  5093.8 2158.97  5111.5 2160.92
  5149.5 2162.94  5192.6 2164.32  5215.4 2165.53  5233.2 2167.26  5304.1 2170.36
#Mann=3,-1,0
  4319.9     0.1       0  5030.8    0.05       0  5035.0     0.1       0
Bank Sta=5030.8,5035
Exp/Cntr=0.3,0.1

Type RM Length L Ch R = 1,7125,439,439,439
BEGIN DESCRIPTION:
Stream0182 16.0
END DESCRIPTION:
XS GIS Cut Line= 3
      1801797.48     13955277.37      1802225.00     13954825.00
      1802025.01     13954025.05
#Sta/Elev= 30
  4377.6 2163.17  4434.3 2161.79  4497.8 2159.03  4582.7 2156.90  4639.4 2156.31
  4646.2 2155.60  4702.9 2154.69  4731.2 2153.33  4837.2 2151.91  4844.5 2152.49
  4858.6 2151.54  4879.7 2151.90  4969.8 2147.48  4970.1 2146.98  4974.1 2147.48
  4992.9 2147.50  4996.6 2148.28  5023.2 2148.41  5123.7 2151.97  5183.0 2152.36
  5257.7 2154.52  5265.5 2155.44  5270.6 2155.02  5360.8 2159.34  5494.8 2164.09
  5554.1 2168.06  5670.0 2172.01  5677.8 2173.16  5742.2 2174.32  5824.6 2179.29
#Mann=3,-1,0
  4377.6     0.1       0  4969.8    0.05       0  4974.1     0.1       0
Bank Sta=4969.8,4974.1
Exp/Cntr=0.3,0.1

Type RM Length L Ch R = 1,6686,469,469,469
BEGIN DESCRIPTION:
Stream0182 15.0
END DESCRIPTION:
XS GIS Cut Line= 3
      1802625.00     13955125.01      1802625.00     13954925.00
      1802174.97     13954174.96
#Sta/Elev= 30
  4800.0 2160.48  4860.0 2156.25  4890.0 2152.80  4910.0 2152.31  4950.0 2146.90
  4960.0 2143.33  4977.6 2139.77  4978.0 2139.27  4982.4 2139.77  4997.5 2141.14
  5013.6 2141.63  5023.3 2143.13  5044.7 2144.87  5050.5 2144.47  5058.3 2145.61
  5167.2 2148.09  5219.6 2148.18  5241.0 2149.57  5291.6 2149.82  5326.5 2150.63
  5349.9 2151.97  5431.5 2153.01  5452.9 2154.35  5575.3 2157.51  5664.7 2161.04
  5707.5 2163.05  5723.0 2164.70  5771.6 2166.40  5793.0 2168.21  5874.7 2170.51
#Mann=3,-1,0
  4800.0     0.1       0  4977.6    0.05       0  4982.4     0.1       0
Bank Sta=4977.6,4982.4
Exp/Cntr=0.3,0.1

Type RM Length L Ch R = 1,6217,464,464,464
BEGIN DESCRIPTION:
Stream0182 14.0
END DESCRIPTION:
XS GIS Cut Line= 3
      1803075.00     13955024.97      1803075.00     13954875.00
      1802824.99     13954574.99
#Sta/Elev= 30
  4850.1 2151.27  4870.1 2150.41  4900.1 2146.91  4950.1 2142.92  4960.1 2139.38
  4970.1 2134.85  4987.6 2132.76  4988.0 2132.26  4992.2 2132.26  4992.5 2132.76
  4997.6 2134.26  5003.3 2134.26  5007.2 2135.52  5013.7 2135.30  5021.5 2137.19
  5028.1 2137.23  5035.9 2138.47  5078.2 2140.62  5085.3 2141.50  5220.7 2144.75
  5227.2 2144.41  5248.0 2144.83  5262.4 2145.92  5276.7 2145.51  5298.8 2146.64
  5305.3 2146.48  5354.8 2147.87  5383.4 2148.14  5387.3 2148.97  5390.6 2148.97
#Mann=3,-1,0
  4850.1     0.1       0  4987.6    0.05       0  4992.5     0.1       0
Bank Sta=4987.6,4992.5
Exp/Cntr=0.3,0.1

Type RM Length L Ch R = 1,5753,410,410,410
BEGIN DESCRIPTION:
Stream0182 13.0
END DESCRIPTION:
XS GIS Cut Line= 3
      1803425.00     13954925.01      1803475.00     13954675.00
      1803525.00     13954325.01
#Sta/Elev= 30
  4750.7 2147.10  4781.3 2146.14  4822.1 2144.04  4832.3 2144.40  4873.1 2141.15
  4893.5 2139.93  4964.9 2132.67  4975.1 2130.45  4982.8 2129.58  4983.2 2129.08
  4987.4 2129.08  4987.7 2129.58  5003.1 2130.43  5015.8 2130.20  5046.1 2131.12
  5066.3 2133.48  5086.5 2134.76  5106.7 2134.87  5126.9 2133.89  5137.0 2132.27
  5147.1 2131.86  5157.2 2132.40  5182.4 2136.05  5207.7 2137.73  5217.8 2139.49
  5238.0 2140.94  5258.2 2141.62  5308.7 2145.05  5339.0 2146.33  5359.2 2146.40
#Mann=3,-1,0
  4750.7     0.1       0  4982.8    0.05       0  4987.7     0.1       0
Bank Sta=4982.8,4987.7
Exp/Cntr=0.3,0.1

Type RM Length L Ch R = 1,5343,444,444,444
BEGIN DESCRIPTION:
Stream0182 12.0
END DESCRIPTION:
XS GIS Cut Line= 3
      1803675.00     13954875.01      1803825.00     13954575.00
      1803940.26     13954053.71
#Sta/Elev= 30
  4656.6 2144.37  4679.0 2143.06  4701.3 2142.99  4871.8 2136.70  4880.2 2137.05
  4969.7 2131.49  4978.0 2129.81  4983.6 2130.08  4989.2 2127.96  4999.6 2127.44
  5000.0 2126.94  5004.9 2127.44  5033.0 2128.75  5043.2 2127.68  5084.2 2128.00
  5094.4 2129.14  5103.7 2131.14  5108.8 2130.95  5114.9 2133.42  5125.2 2136.18
  5152.5 2140.93  5157.6 2140.79  5250.0 2147.60  5330.0 2151.48  5337.3 2152.69
  5371.0 2154.78  5504.1 2160.37  5514.3 2160.88  5522.1 2162.30  5525.9 2161.82
#Mann=3,-1,0
  4656.6     0.1       0  4999.6    0.05       0  5004.9     0.1       0
Bank Sta=4999.6,5004.9
Exp/Cntr=0.3,0.1

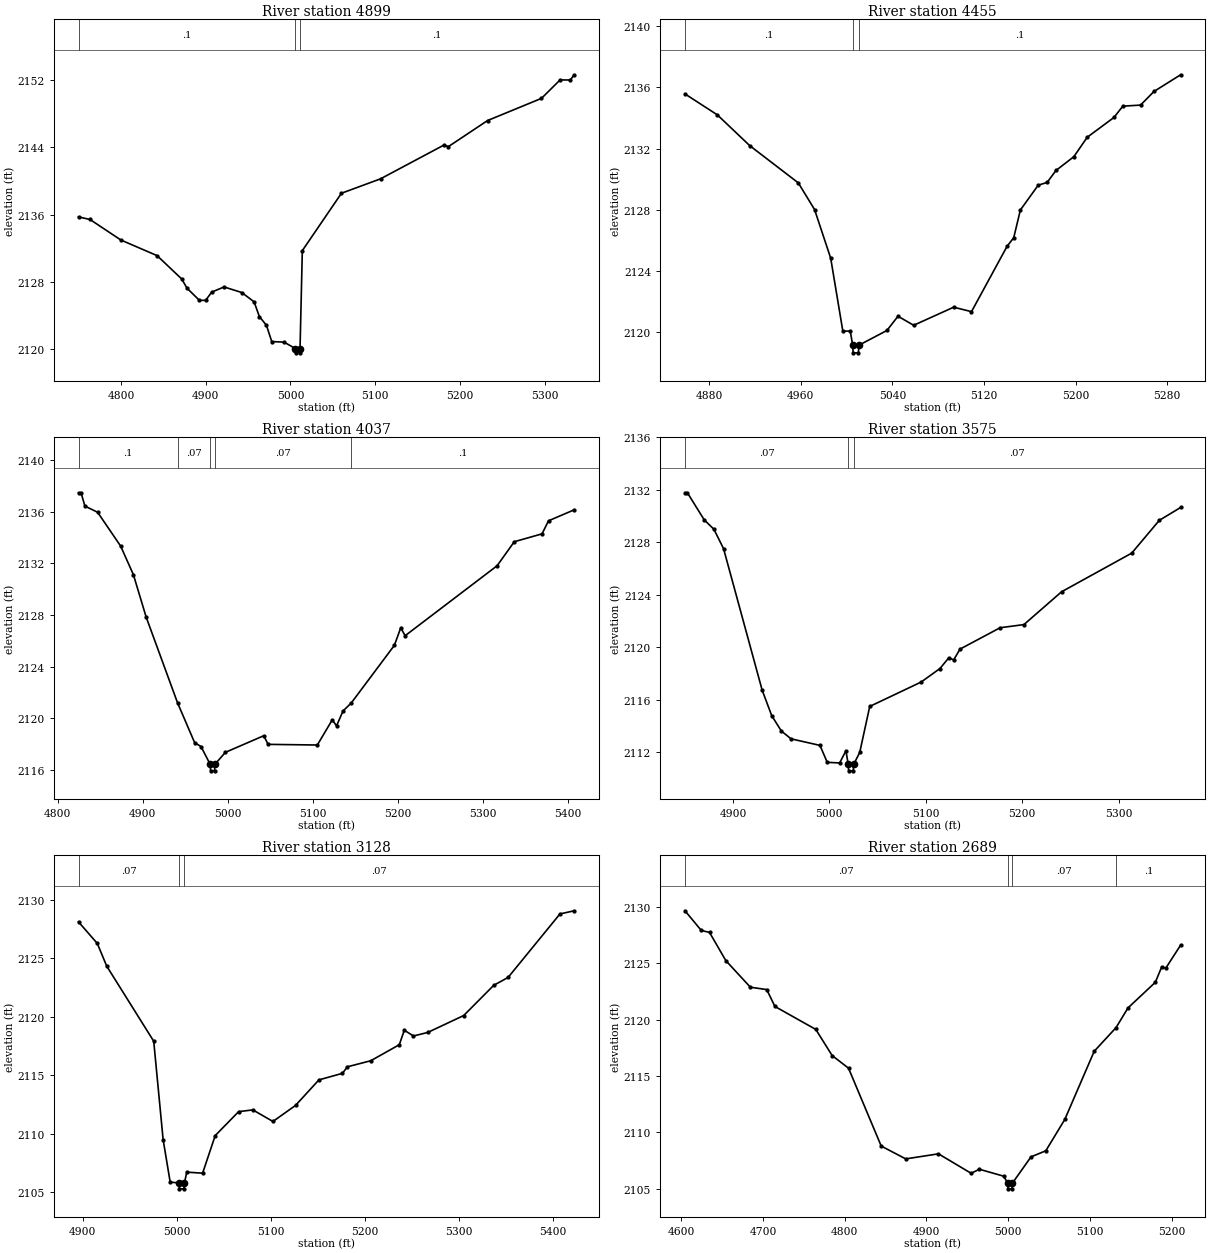
Type RM Length L Ch R = 1,4899,444,444,444
BEGIN DESCRIPTION:
Stream0182 11.0
END DESCRIPTION:
XS GIS Cut Line= 3
      1804025.02     13954824.97      1804175.00     13954625.00
      1804313.64     13954319.88
#Sta/Elev= 30
  4749.8 2135.73  4763.3 2135.43  4799.8 2132.99  4842.5 2131.14  4871.6 2128.37
  4877.9 2127.27  4892.5 2125.83  4899.8 2125.83  4907.1 2126.81  4921.6 2127.42
  4942.5 2126.76  4957.1 2125.65  4963.3 2123.90  4971.6 2122.88  4977.9 2120.94
  4992.5 2120.87  5005.9 2120.10  5006.3 2119.60  5010.8 2119.60  5011.3 2120.10
  5014.0 2131.73  5060.2 2138.54  5106.3 2140.25  5181.0 2144.25  5186.5 2144.08
  5232.7 2147.17  5296.3 2149.80  5318.3 2151.99  5330.4 2151.98  5334.9 2152.60
#Mann=3,-1,0
  4749.8     0.1       0  5005.9    0.05       0  5011.3     0.1       0
Bank Sta=5005.9,5011.3
Exp/Cntr=0.3,0.1

Type RM Length L Ch R = 1,4455,418,418,418
BEGIN DESCRIPTION:
Stream0182 10.0
END DESCRIPTION:
XS GIS Cut Line= 3
      1804324.98     13955075.02      1804425.00     13954975.00
      1804575.00     13954724.99
#Sta/Elev= 30
  4858.8 2135.58  4887.1 2134.21  4915.4 2132.20  4957.8 2129.77  4972.0 2128.03
  4986.1 2124.85  4996.7 2120.09  5003.2 2120.09  5005.3 2119.17  5005.7 2118.67
  5010.3 2118.67  5010.8 2119.17  5035.2 2120.13  5044.9 2121.06  5058.6 2120.47
  5093.5 2121.65  5109.1 2121.36  5140.2 2125.63  5146.0 2126.19  5151.8 2128.00
  5167.4 2129.62  5175.2 2129.80  5182.9 2130.58  5198.5 2131.48  5210.2 2132.75
  5233.5 2134.04  5241.3 2134.78  5256.8 2134.85  5268.5 2135.74  5291.8 2136.83
#Mann=3,-1,0
  4858.8     0.1       0  5005.3    0.05       0  5010.8     0.1       0
Bank Sta=5005.3,5010.8
Exp/Cntr=0.3,0.1

Type RM Length L Ch R = 1,4037,462,462,462
BEGIN DESCRIPTION:
Stream0182 9.0
END DESCRIPTION:
XS GIS Cut Line= 3
      1804674.99     13955325.01      1804775.00     13955175.00
      1804725.00     13954775.00
#Sta/Elev= 30
  4824.4 2137.46  4827.4 2137.46  4831.9 2136.43  4846.9 2135.95  4874.0 2133.33
  4889.0 2131.12  4904.0 2127.84  4941.0 2121.19  4961.1 2118.11  4968.6 2117.81
  4979.4 2116.43  4979.9 2115.93  4984.5 2115.93  4984.9 2116.43  4997.2 2117.36
  5042.5 2118.65  5047.5 2117.98  5105.5 2117.93  5123.1 2119.88  5128.1 2119.41
  5135.7 2120.56  5145.5 2121.19  5196.2 2125.65  5203.7 2127.01  5208.8 2126.39
  5317.1 2131.81  5337.3 2133.67  5370.0 2134.28  5377.6 2135.29  5407.8 2136.14
#Mann=5,-1,0
  4824.4     0.1       0  4941.0    0.07       0  4979.4    0.05       0
  4984.9    0.07       0  5145.5     0.1       0
Bank Sta=4979.4,4984.9
Exp/Cntr=0.3,0.1

Type RM Length L Ch R = 1,3575,447,447,447
BEGIN DESCRIPTION:
Stream0182 8.0
END DESCRIPTION:
XS GIS Cut Line= 3
      1805175.00     13955425.01      1805175.00     13955275.00
      1805075.00     13954925.02
#Sta/Elev= 30
  4850.3 2131.78  4852.8 2131.78  4870.3 2129.71  4880.3 2129.00  4890.3 2127.52
  4930.3 2116.74  4940.3 2114.78  4950.3 2113.61  4960.3 2113.02  4990.3 2112.52
  4997.8 2111.23  5010.7 2111.18  5017.2 2112.11  5019.6 2111.08  5020.0 2110.58
  5024.8 2110.58  5025.3 2111.08  5031.5 2111.98  5041.9 2115.49  5095.2 2117.35
  5114.7 2118.38  5123.8 2119.19  5129.0 2119.04  5135.5 2119.86  5177.1 2121.49
  5201.8 2121.73  5240.8 2124.23  5313.6 2127.18  5342.2 2129.68  5364.3 2130.66
#Mann=3,-1,0
  4850.3    0.07       0  5019.6    0.05       0  5025.3    0.07       0
Bank Sta=5019.6,5025.3
Exp/Cntr=0.3,0.1

Type RM Length L Ch R = 1,3128,439,439,439
BEGIN DESCRIPTION:
Stream0182 7.0
END DESCRIPTION:
XS GIS Cut Line= 3
      1805575.00     13955324.99      1805575.00     13955225.00
      1805425.00     13954824.99
#Sta/Elev= 30
  4895.5 2128.13  4915.5 2126.28  4925.5 2124.34  4975.5 2117.91  4985.5 2109.48
  4993.0 2105.85  5002.4 2105.77  5002.9 2105.27  5007.7 2105.27  5008.2 2105.77
  5010.6 2106.70  5027.5 2106.61  5040.9 2109.83  5065.8 2111.88  5080.9 2112.03
  5102.3 2111.04  5126.3 2112.41  5151.2 2114.60  5176.2 2115.16  5181.5 2115.72
  5206.4 2116.24  5236.7 2117.61  5242.0 2118.85  5251.8 2118.36  5266.9 2118.66
  5305.2 2120.11  5337.2 2122.70  5352.4 2123.37  5407.6 2128.81  5422.7 2129.08
#Mann=3,-1,0
  4895.5    0.07       0  5002.4    0.05       0  5008.2    0.07       0
Bank Sta=5002.4,5008.2
Exp/Cntr=0.3,0.1

Type RM Length L Ch R = 1,2689,433,433,433
BEGIN DESCRIPTION:
Stream0182 6.0
END DESCRIPTION:
XS GIS Cut Line= 3
      1805875.00     13955325.03      1805875.00     13954925.00
      1805825.00     13954724.99
#Sta/Elev= 30
  4604.7 2129.68  4624.7 2127.93  4634.7 2127.76  4654.7 2125.25  4684.7 2122.89
  4704.7 2122.68  4714.7 2121.18  4764.7 2119.14  4784.7 2116.82  4804.7 2115.70
  4844.7 2108.78  4874.7 2107.64  4914.7 2108.09  4954.7 2106.36  4964.7 2106.72
  4994.7 2106.10  4999.3 2105.48  4999.8 2104.98  5004.7 2104.98  5005.1 2105.48
  5027.9 2107.82  5046.0 2108.36  5069.2 2111.14  5105.2 2117.20  5131.9 2119.30
  5146.5 2121.05  5180.0 2123.33  5187.7 2124.69  5192.8 2124.59  5210.9 2126.63
#Mann=4,-1,0
  4604.7    0.07       0  4999.3    0.05       0  5005.1    0.07       0
  5131.9     0.1       0
Bank Sta=4999.3,5005.1
Exp/Cntr=0.3,0.1

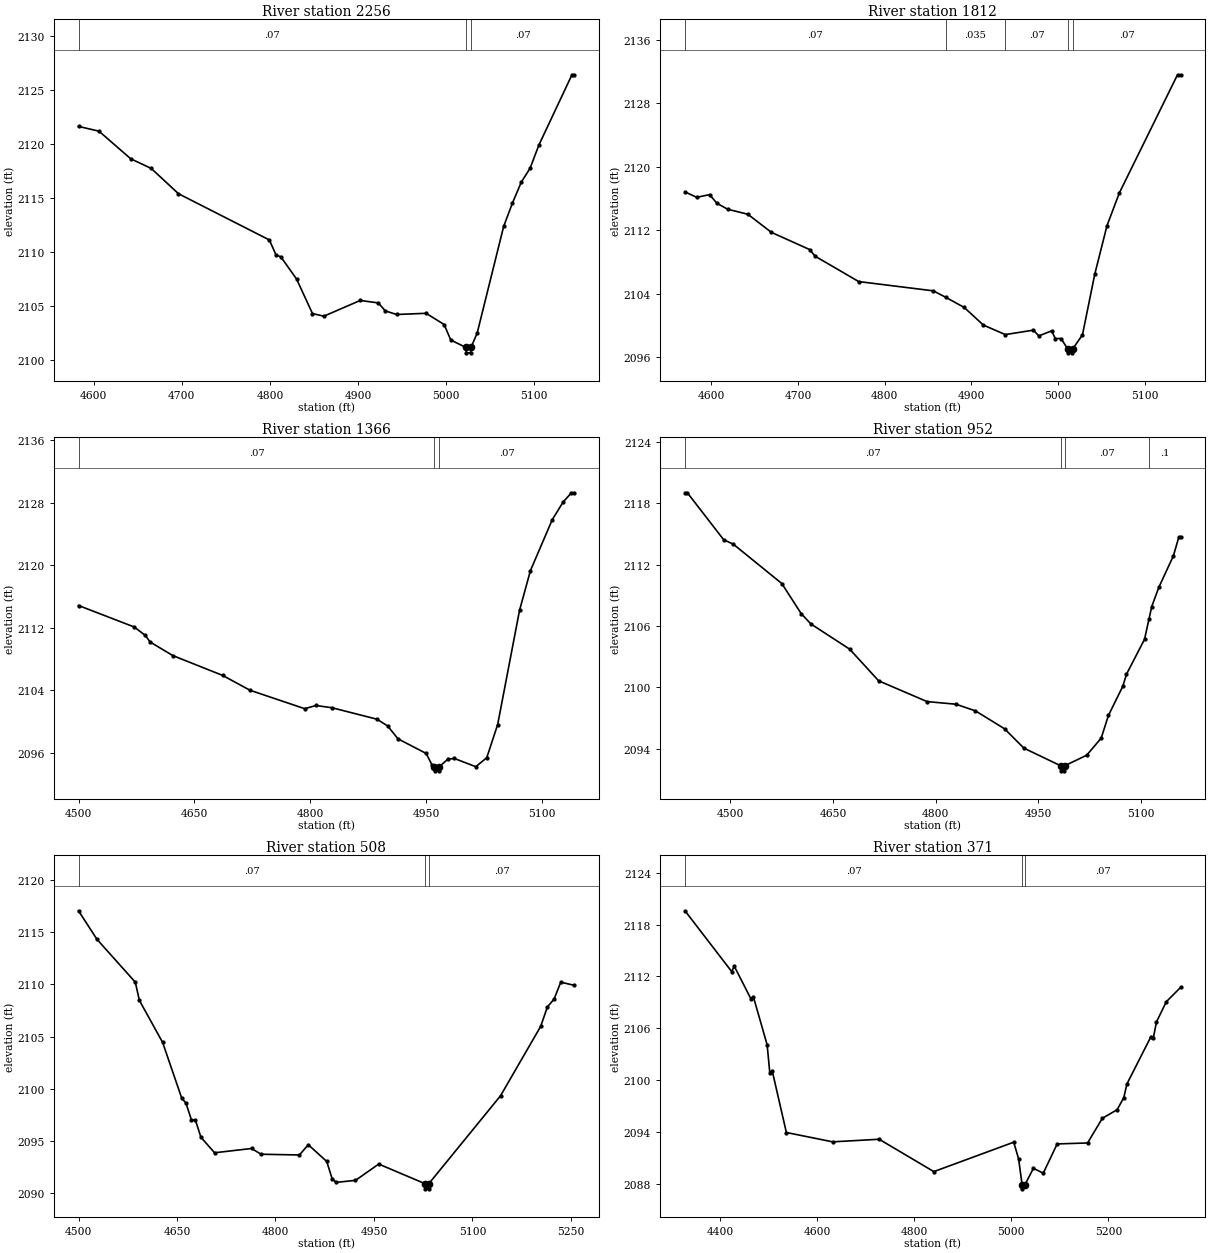
Type RM Length L Ch R = 1,2256,444,444,444
BEGIN DESCRIPTION:
Stream0182 5.0
END DESCRIPTION:
XS GIS Cut Line= 3
      1806174.99     13955225.02      1806275.00     13954825.00
      1806275.00     13954675.03
#Sta/Elev= 30
  4582.9 2121.59  4606.1 2121.15  4642.2 2118.59  4665.4 2117.70  4696.3 2115.36
  4799.4 2111.08  4807.1 2109.67  4812.3 2109.53  4830.3 2107.46  4848.3 2104.27
  4861.2 2104.02  4902.5 2105.48  4923.1 2105.25  4930.8 2104.52  4943.7 2104.18
  4977.2 2104.29  4997.7 2103.25  5005.2 2101.82  5022.3 2101.13  5022.8 2100.63
  5027.7 2100.63  5028.2 2101.13  5035.2 2102.47  5065.2 2112.33  5075.2 2114.50
  5085.2 2116.43  5095.2 2117.72  5105.2 2119.87  5142.7 2126.37  5145.2 2126.37
#Mann=3,-1,0
  4582.9    0.07       0  5022.3    0.05       0  5028.2    0.07       0
Bank Sta=5022.3,5028.2
Exp/Cntr=0.3,0.1

Type RM Length L Ch R = 1,1812,446,446,446
BEGIN DESCRIPTION:
Stream0182 4.0
END DESCRIPTION:
XS GIS Cut Line= 3
      1806424.98     13955225.02      1806675.00     13954875.00
      1806775.02     13954774.98
#Sta/Elev= 30
  4569.8 2116.84  4583.3 2116.15  4598.1 2116.49  4606.7 2115.40  4619.0 2114.65
  4642.3 2114.02  4669.4 2111.74  4713.6 2109.57  4719.8 2108.74  4770.1 2105.54
  4856.2 2104.37  4870.3 2103.57  4891.8 2102.28  4913.9 2100.06  4939.2 2098.86
  4971.7 2099.42  4977.8 2098.69  4992.6 2099.33  4996.9 2098.36  5003.5 2098.36
  5011.1 2097.06  5011.6 2096.56  5016.6 2096.56  5017.0 2097.06  5028.2 2098.83
  5042.4 2106.48  5056.5 2112.59  5070.7 2116.70  5137.8 2131.59  5141.4 2131.59
#Mann=5,-1,0
  4569.8    0.07       0  4870.3   0.035       0  4939.2    0.07       0
  5011.1    0.05       0  5017.0    0.07       0
Bank Sta=5011.1,5017
Exp/Cntr=0.3,0.1

Type RM Length L Ch R = 1,1366,414,414,414
BEGIN DESCRIPTION:
Stream0182 3.0
END DESCRIPTION:
XS GIS Cut Line= 3
      1806575.02     13955474.99      1806975.00     13955175.00
      1807075.00     13955075.00
#Sta/Elev= 30
  4500.0 2114.84  4571.9 2112.10  4586.4 2111.02  4592.7 2110.17  4621.9 2108.44
  4686.4 2105.90  4721.9 2104.00  4792.7 2101.64  4807.3 2102.05  4828.1 2101.76
  4886.4 2100.29  4900.0 2099.43  4913.5 2097.78  4950.0 2095.91  4957.3 2094.46
  4960.5 2094.19  4961.0 2093.69  4966.0 2093.69  4966.5 2094.19  4978.1 2095.19
  4986.4 2095.27  5014.1 2094.22  5028.3 2095.37  5042.4 2099.61  5070.7 2114.22
  5084.8 2119.30  5113.1 2125.83  5127.3 2128.10  5137.9 2129.26  5141.4 2129.26
#Mann=3,-1,0
  4500.0    0.07       0  4960.5    0.05       0  4966.5    0.07       0
Bank Sta=4960.5,4966.5
Exp/Cntr=0.3,0.1

Type RM Length L Ch R = 1,952,444,444,444
BEGIN DESCRIPTION:
Stream0182 2.0
END DESCRIPTION:
XS GIS Cut Line= 3
      1806825.02     13955874.98      1807225.00     13955475.00
      1807275.01     13955324.97
#Sta/Elev= 30
  4433.9 2119.03  4437.4 2119.03  4490.4 2114.44  4504.6 2114.00  4575.3 2110.16
  4603.6 2107.22  4617.7 2106.21  4674.3 2103.75  4716.7 2100.65  4787.4 2098.62
  4829.8 2098.36  4858.1 2097.71  4900.6 2095.96  4928.8 2094.07  4982.4 2092.35
  4982.9 2091.85  4988.0 2091.85  4988.5 2092.35  5020.6 2093.38  5041.7 2095.05
  5052.3 2097.27  5073.3 2100.12  5078.6 2101.29  5105.0 2104.71  5111.5 2106.69
  5115.5 2107.91  5126.0 2109.81  5147.1 2112.86  5155.0 2114.69  5157.7 2114.69
#Mann=4,-1,0
  4433.9    0.07       0  4982.4    0.05       0  4988.5    0.07       0
  5111.5     0.1       0
Bank Sta=4982.4,4988.5
Exp/Cntr=0.3,0.1

Type RM Length L Ch R = 1,508,137,137,137
BEGIN DESCRIPTION:
Stream0182 1.0
END DESCRIPTION:
XS GIS Cut Line= 3
      1807124.99     13956075.01      1807525.00     13955775.00
      1807575.01     13955524.96
#Sta/Elev= 30
  4500.0 2117.04  4528.1 2114.31  4586.5 2110.21  4592.7 2108.47  4628.1 2104.45
  4657.3 2099.10  4663.6 2098.65  4671.9 2097.06  4678.1 2097.01  4686.5 2095.37
  4707.3 2093.89  4763.6 2094.30  4778.1 2093.75  4836.5 2093.68  4850.0 2094.66
  4878.1 2093.06  4886.5 2091.37  4892.7 2091.06  4921.9 2091.25  4957.3 2092.81
  5027.6 2090.94  5028.1 2090.44  5033.2 2090.44  5033.7 2090.94  5142.8 2099.34
  5204.0 2105.98  5214.2 2107.84  5224.4 2108.59  5234.6 2110.21  5255.0 2109.91
#Mann=3,-1,0
  4500.0    0.07       0  5027.6    0.05       0  5033.7    0.07       0
Bank Sta=5027.6,5033.7
Exp/Cntr=0.3,0.1

Type RM Length L Ch R = 1,371,0,0,0
BEGIN DESCRIPTION:
Stream0182 0.0
END DESCRIPTION:
XS GIS Cut Line= 4
      1807081.99     13956147.35      1807600.36     13956001.81
      1807645.96     13955739.35      1807610.66     13955525.85
#Sta/Elev= 30
  4327.7 2119.59  4424.0 2112.56  4429.2 2113.19  4463.3 2109.44  4468.5 2109.68
  4497.0 2104.10  4502.5 2100.83  4507.7 2101.03  4536.6 2093.97  4632.0 2092.89
  4727.8 2093.19  4840.4 2089.45  5005.0 2092.85  5015.1 2090.92  5022.2 2087.96
  5022.7 2087.46  5028.3 2087.96  5045.6 2089.83  5065.9 2089.27  5094.5 2092.65
  5157.2 2092.76  5187.6 2095.61  5218.0 2096.60  5231.8 2098.00  5238.3 2099.59
  5287.8 2105.05  5292.8 2104.93  5299.1 2106.74  5319.4 2109.08  5348.9 2110.74
#Mann=3,-1,0
  4327.7    0.07       0  5022.2    0.05       0  5028.3    0.07       0
Bank Sta=5022.2,5028.3
Exp/Cntr=0.3,0.1

Chan Stop Cuts=-1