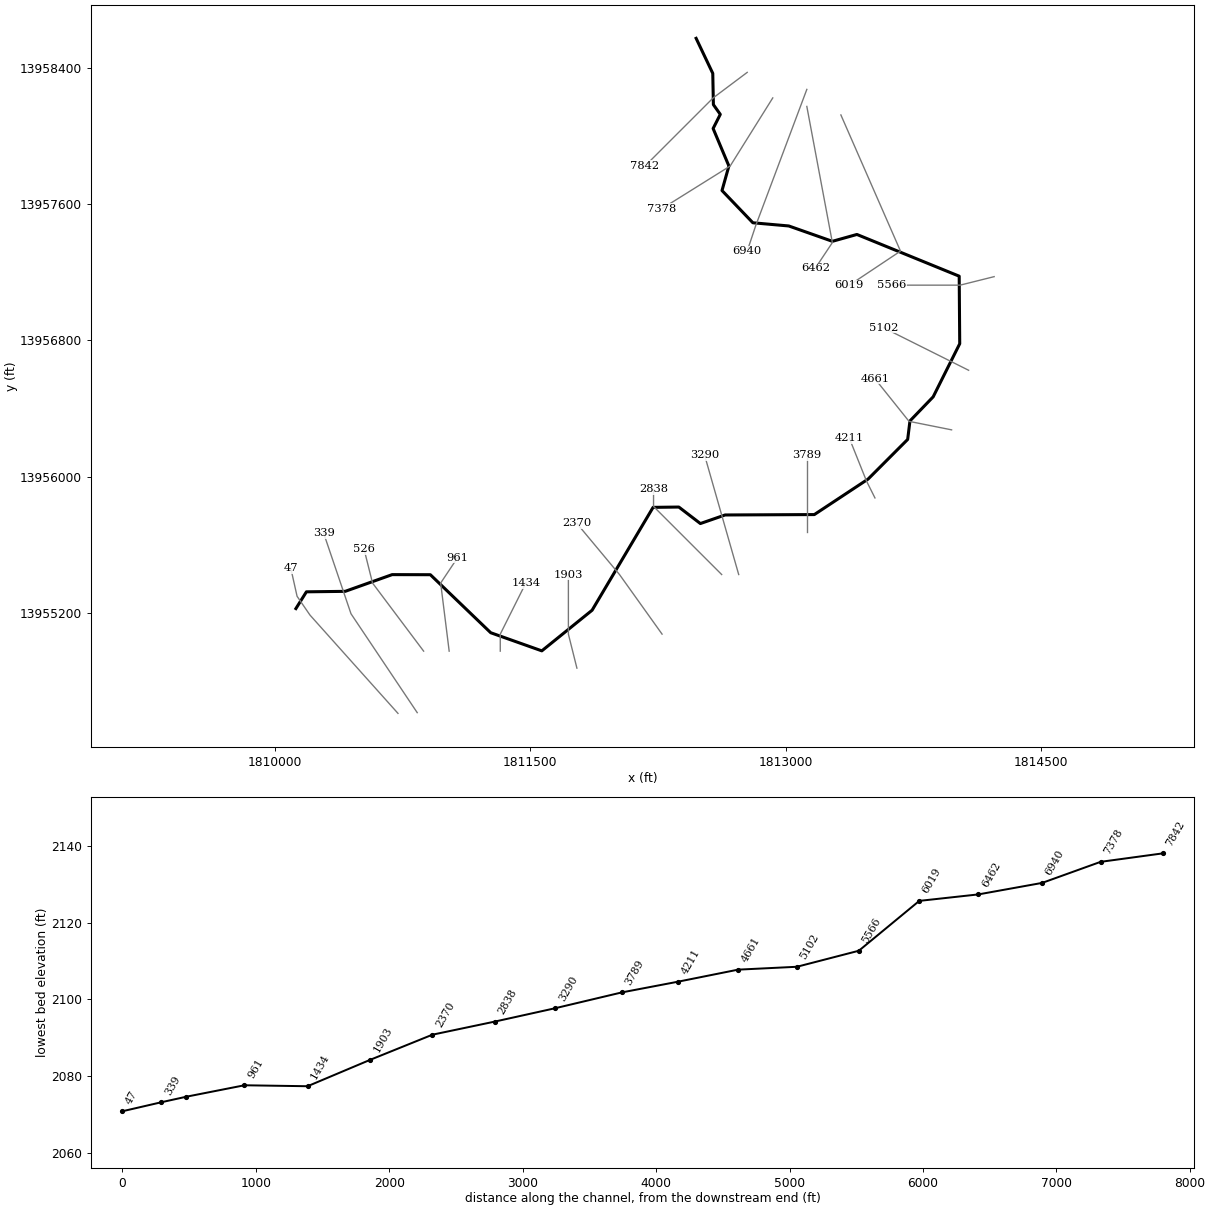
--- Stream0183.prj (project) ---

Proj Title=Stream0183 Base Level Engineering
Current Plan=p01
Default Exp/Contr=0.3,0.1
English Units
Geom File=g01
Flow File=f01
Plan File=p01
BEGIN DESCRIPTION:
Stream0183
END DESCRIPTION:

--- Stream0183.p01 (plan) ---

Plan Title=Multiple Run
Short Identifier=Multiple
Geom File=g01
Flow File=f01
Subcritical Flow
K Sum by GR= 0
Std Step Tol= 0.01
Critical Tol= 0.01
Num of Std Step Trials= 20
Max Error Tol= 0.3
Flow Tol Ratio= 0.001
Split Flow NTrial= 30
Split Flow Tol= 0.02
Split Flow Ratio= 0.02
Log Output Level= 0
Friction Slope Method= 1
Unsteady Friction Slope Method= 2
Unsteady Bridges Friction Slope Method= 1
Parabolic Critical Depth
Global Vel Dist=  1 , 1 , 1
Global Log Level= 0
CheckData=True
Encroach Param= -1, 0, 0, 0
BEGIN DESCRIPTION:
Multiple Run
END DESCRIPTION:

--- Stream0183.f01 (steady flow) ---

Flow Title=Multiple
Number of Profiles=7
Profile Names=10-year,25-year,50-year,1pct_min,100-year,1pct_plu,500-year
River Rch & RM= Stream0183,Reach-1,7842
    1741    3032    4282    2915    5815   11603   10612
River Rch & RM= Stream0183,Reach-1,4211
    1962    3448    4897    3349    6682   13333   12323
Boundary for River Rch & Prof#=Stream0183,Reach-1,1
Up Type=0
Dn Type=3
Dn Slope=0.005
Boundary for River Rch & Prof#=Stream0183,Reach-1,2
Up Type=0
Dn Type=3
Dn Slope=0.005
Boundary for River Rch & Prof#=Stream0183,Reach-1,3
Up Type=0
Dn Type=3
Dn Slope=0.005
Boundary for River Rch & Prof#=Stream0183,Reach-1,4
Up Type=0
Dn Type=3
Dn Slope=0.005
Boundary for River Rch & Prof#=Stream0183,Reach-1,5
Up Type=0
Dn Type=3
Dn Slope=0.005
Boundary for River Rch & Prof#=Stream0183,Reach-1,6
Up Type=0
Dn Type=3
Dn Slope=0.005
Boundary for River Rch & Prof#=Stream0183,Reach-1,7
Up Type=0
Dn Type=3
Dn Slope=0.005

--- Stream0183.g01 (geometry) ---

Geom Title=Existing Conditions

River Reach=Stream0183,Reach-1
Reach XY= 30
      1812475.00     13958575.00      1812572.76     13958369.07
      1812576.38     13958185.44      1812616.89     13958128.29
      1812574.79     13958045.21      1812667.44     13957825.00
      1812626.97     13957680.89      1812808.24     13957491.43
      1813019.06     13957472.74      1813275.00     13957382.56
      1813419.02     13957422.83      1814019.66     13957177.74
      1814022.76     13956780.93      1813866.86     13956468.94
      1813730.52     13956327.43      1813717.14     13956218.83
      1813484.68     13955985.78      1813169.07     13955777.24
      1812645.03     13955774.93      1812499.96     13955724.51
      1812373.53     13955821.46      1812222.30     13955819.65
      1811864.22     13955215.32      1811568.96     13954976.63
      1811268.94     13955083.14      1810914.57     13955423.95
      1810690.22     13955424.48      1810414.50     13955326.22
      1810186.71     13955323.46      1810125.00     13955225.00

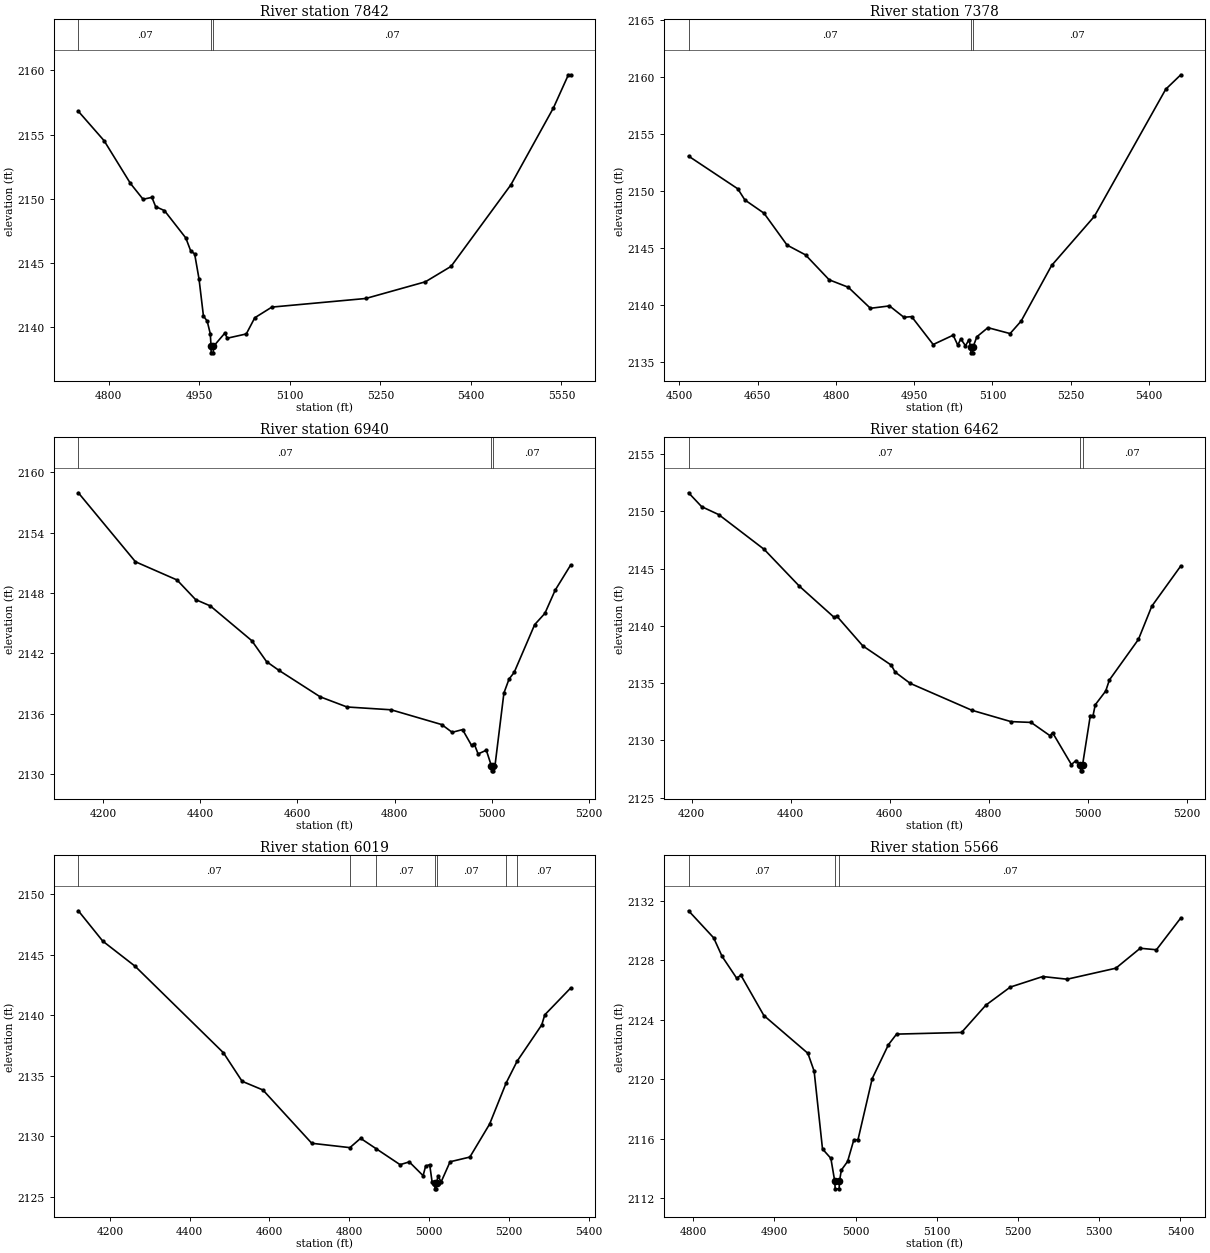
Type RM Length L Ch R = 1,7842,464,464,464
BEGIN DESCRIPTION:
Stream0183 17.0
END DESCRIPTION:
XS GIS Cut Line= 3
      1812774.98     13958374.99      1812575.00     13958225.00
      1812174.97     13957824.97
#Sta/Elev= 30
  4749.5 2156.82  4792.2 2154.53  4835.9 2151.20  4856.8 2149.97  4871.4 2150.12
  4877.6 2149.40  4892.2 2149.09  4927.6 2146.96  4935.9 2145.93  4942.2 2145.73
  4949.5 2143.77  4956.8 2140.89  4963.0 2140.49  4968.2 2139.50  4969.4 2138.52
  4969.6 2138.02  4973.1 2138.02  4973.4 2138.52  4992.2 2139.55  4996.4 2139.16
  5027.8 2139.49  5041.9 2140.75  5070.2 2141.58  5225.8 2142.25  5324.7 2143.55
  5367.2 2144.75  5466.2 2151.09  5536.9 2157.09  5561.6 2159.66  5565.2 2159.66
#Mann=3,-1,0
  4749.5    0.07       0  4969.4    0.05       0  4973.4    0.07       0
Bank Sta=4969.4,4973.4
Exp/Cntr=0.3,0.1

Type RM Length L Ch R = 1,7378,438,438,438
BEGIN DESCRIPTION:
Stream0183 16.0
END DESCRIPTION:
XS GIS Cut Line= 3
      1812925.00     13958225.00      1812675.00     13957825.00
      1812275.00     13957575.00
#Sta/Elev= 30
  4517.6 2153.09  4611.9 2150.22  4625.5 2149.24  4662.1 2148.08  4706.3 2145.28
  4741.7 2144.42  4787.1 2142.23  4823.6 2141.58  4866.1 2139.73  4902.6 2139.94
  4930.3 2138.94  4945.1 2139.00  4986.4 2136.55  5024.7 2137.37  5033.5 2136.50
  5039.4 2137.04  5048.3 2136.44  5054.7 2136.95  5058.6 2136.32  5058.8 2135.82
  5062.4 2135.82  5062.7 2136.32  5070.1 2137.23  5091.3 2138.03  5133.8 2137.51
  5155.0 2138.61  5213.4 2143.49  5295.3 2147.80  5432.1 2158.96  5461.0 2160.23
#Mann=3,-1,0
  4517.6    0.07       0  5058.6    0.05       0  5062.7    0.07       0
Bank Sta=5058.6,5062.7
Exp/Cntr=0.3,0.1

Type RM Length L Ch R = 1,6940,478,478,478
BEGIN DESCRIPTION:
Stream0183 15.0
END DESCRIPTION:
XS GIS Cut Line= 3
      1813125.01     13958275.04      1812825.00     13957475.00
      1812774.98     13957324.95
#Sta/Elev= 30
  4149.4 2157.98  4266.9 2151.12  4352.4 2149.31  4390.6 2147.36  4420.9 2146.73
  4506.3 2143.27  4536.6 2141.19  4561.5 2140.34  4646.9 2137.69  4702.1 2136.68
  4792.9 2136.40  4897.0 2134.93  4918.4 2134.16  4939.8 2134.43  4958.4 2132.85
  4963.8 2133.01  4971.8 2132.01  4988.7 2132.38  4999.1 2130.83  4999.4 2130.33
  5003.0 2130.33  5003.2 2130.83  5006.5 2130.83  5024.9 2138.07  5035.5 2139.46
  5046.0 2140.12  5088.2 2144.87  5109.2 2145.99  5130.3 2148.29  5162.0 2150.78
#Mann=3,-1,0
  4149.4    0.07       0  4999.1    0.05       0  5003.2    0.07       0
Bank Sta=4999.1,5003.2
Exp/Cntr=0.3,0.1

Type RM Length L Ch R = 1,6462,443,443,443
BEGIN DESCRIPTION:
Stream0183 14.0
END DESCRIPTION:
XS GIS Cut Line= 3
      1813125.00     13958174.99      1813275.00     13957375.00
      1813175.00     13957225.01
#Sta/Elev= 30
  4194.0 2151.62  4220.3 2150.41  4255.0 2149.71  4346.6 2146.68  4417.8 2143.46
  4488.2 2140.73  4493.3 2140.85  4545.8 2138.25  4603.5 2136.56  4611.1 2135.96
  4641.7 2134.97  4766.3 2132.62  4845.1 2131.63  4885.8 2131.56  4924.0 2130.40
  4929.1 2130.67  4967.2 2127.88  4976.6 2128.23  4985.5 2127.83  4985.8 2127.33
  4989.4 2127.33  4989.7 2127.83  5005.4 2132.15  5010.9 2132.15  5015.4 2133.10
  5036.5 2134.30  5044.0 2135.27  5102.6 2138.81  5129.6 2141.71  5188.2 2145.23
#Mann=3,-1,0
  4194.0    0.07       0  4985.5    0.05       0  4989.7    0.07       0
Bank Sta=4985.5,4989.7
Exp/Cntr=0.3,0.1

Type RM Length L Ch R = 1,6019,453,453,453
BEGIN DESCRIPTION:
Stream0183 13.0
END DESCRIPTION:
XS GIS Cut Line= 3
      1813325.01     13958124.98      1813675.00     13957325.00
      1813374.96     13957124.97
#Sta/Elev= 30
  4121.1 2148.65  4182.3 2146.14  4263.4 2144.06  4484.8 2136.90  4531.6 2134.54
  4583.8 2133.82  4706.2 2129.41  4801.8 2129.05  4828.6 2129.82  4868.1 2128.95
  4927.6 2127.64  4950.6 2127.87  4985.3 2126.73  4991.6 2127.52  5001.8 2127.64
  5007.8 2126.22  5014.7 2126.14  5015.0 2125.64  5018.6 2125.64  5018.9 2126.14
  5022.8 2126.70  5030.4 2126.21  5052.9 2127.88  5102.5 2128.27  5152.0 2131.00
  5193.4 2134.40  5220.9 2136.20  5282.7 2139.21  5290.3 2140.04  5354.9 2142.25
#Mann=7,-1,0
  4121.1    0.07       0  4801.8     0.1       0  4868.1    0.07       0
  5014.7    0.05       0  5018.9    0.07       0  5193.4     0.1       0
  5220.9    0.07       0
Bank Sta=5014.7,5018.9
Exp/Cntr=0.3,0.1

Type RM Length L Ch R = 1,5566,464,464,464
BEGIN DESCRIPTION:
Stream0183 12.0
END DESCRIPTION:
XS GIS Cut Line= 3
      1814224.97     13957174.99      1814025.00     13957125.00
      1813625.02     13957125.00
#Sta/Elev= 30
  4794.3 2131.33  4825.2 2129.51  4835.5 2128.27  4853.5 2126.80  4858.7 2127.00
  4887.0 2124.29  4941.2 2121.75  4948.9 2120.55  4959.2 2115.32  4969.5 2114.69
  4974.3 2113.14  4974.8 2112.64  4979.7 2112.64  4980.1 2113.14  4982.4 2113.90
  4990.1 2114.48  4997.8 2115.94  5002.9 2115.94  5020.4 2120.05  5040.4 2122.33
  5050.4 2123.04  5130.4 2123.15  5160.4 2124.99  5190.4 2126.20  5230.4 2126.91
  5260.4 2126.73  5320.4 2127.47  5350.4 2128.81  5370.4 2128.71  5400.4 2130.85
#Mann=3,-1,0
  4794.3    0.07       0  4974.3    0.05       0  4980.1    0.07       0
Bank Sta=4974.3,4980.1
Exp/Cntr=0.3,0.1

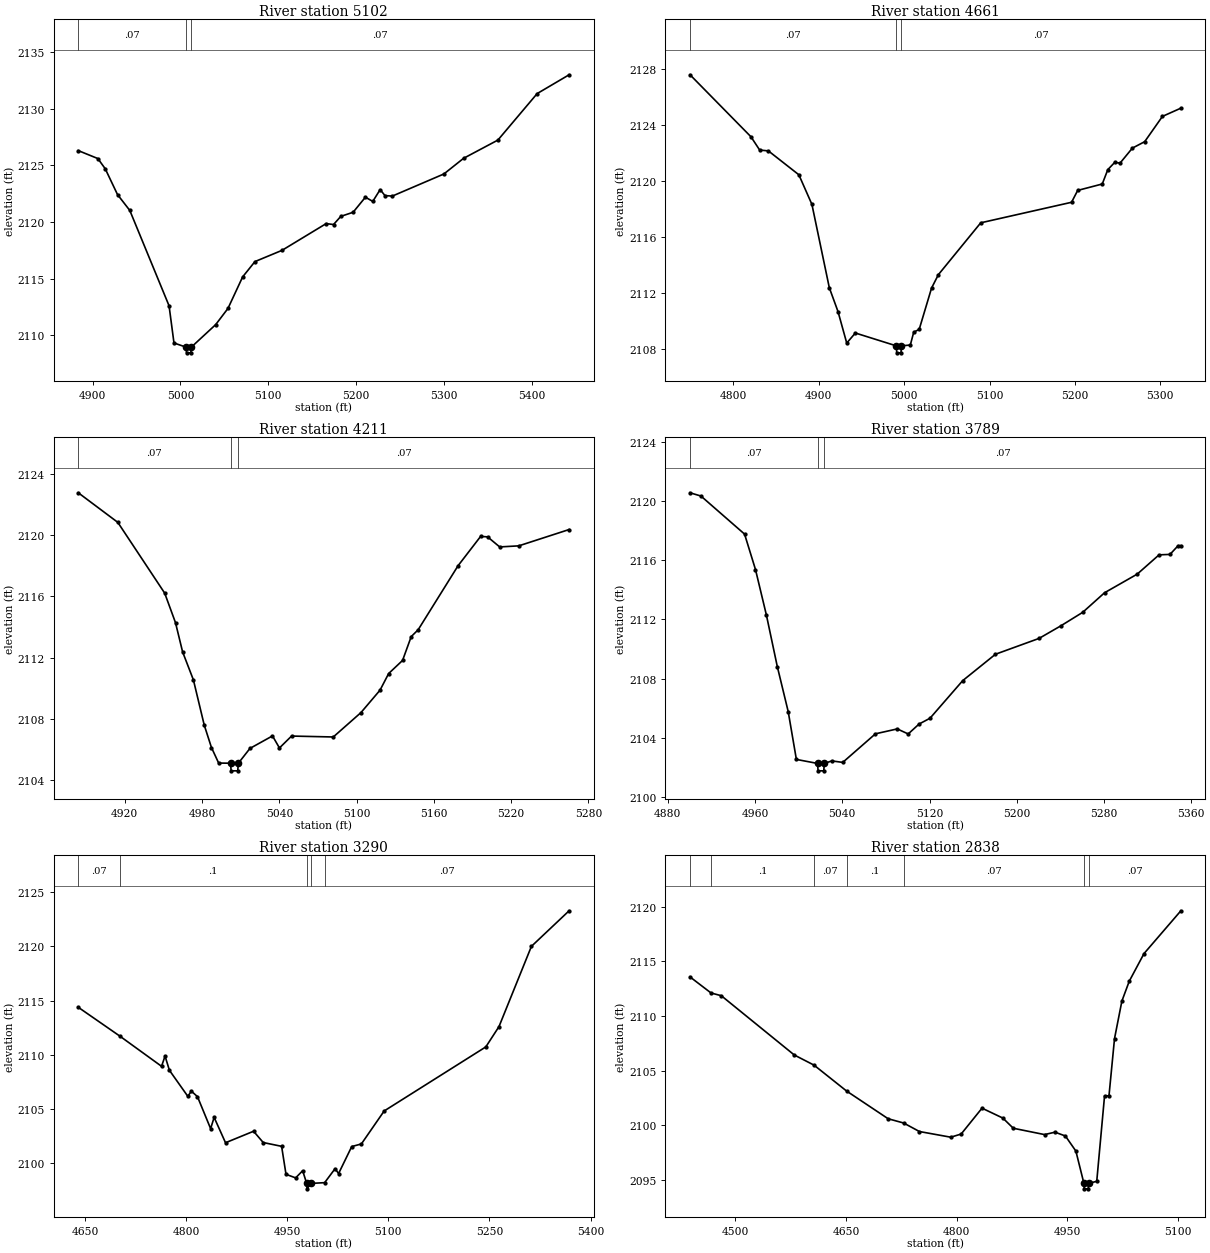
Type RM Length L Ch R = 1,5102,441,441,441
BEGIN DESCRIPTION:
Stream0183 11.0
END DESCRIPTION:
XS GIS Cut Line= 3
      1814074.97     13956625.02      1813975.00     13956675.00
      1813574.98     13956875.01
#Sta/Elev= 30
  4883.7 2126.30  4906.0 2125.60  4914.4 2124.70  4928.4 2122.42  4942.4 2121.02
  4987.1 2112.61  4992.7 2109.33  5006.5 2108.96  5007.0 2108.46  5011.9 2108.46
  5012.4 2108.96  5040.2 2110.95  5054.2 2112.38  5070.9 2115.16  5084.9 2116.51
  5115.7 2117.50  5166.0 2119.86  5174.4 2119.78  5182.7 2120.50  5196.7 2120.86
  5210.7 2122.19  5219.1 2121.82  5227.5 2122.86  5233.0 2122.33  5241.4 2122.29
  5300.1 2124.24  5322.5 2125.62  5361.6 2127.23  5406.3 2131.33  5442.7 2132.99
#Mann=3,-1,0
  4883.7    0.07       0  5006.5    0.05       0  5012.4    0.07       0
Bank Sta=5006.5,5012.4
Exp/Cntr=0.3,0.1

Type RM Length L Ch R = 1,4661,450,450,450
BEGIN DESCRIPTION:
Stream0183 10.0
END DESCRIPTION:
XS GIS Cut Line= 3
      1813974.99     13956275.00      1813725.00     13956325.00
      1813525.00     13956575.01
#Sta/Elev= 30
  4749.1 2127.62  4820.5 2123.18  4830.7 2122.23  4840.9 2122.17  4876.6 2120.46
  4891.9 2118.34  4912.3 2112.37  4922.5 2110.66  4932.7 2108.41  4942.8 2109.13
  4990.8 2108.21  4991.3 2107.71  4996.3 2107.71  4996.8 2108.21  5007.2 2108.27
  5011.2 2109.19  5017.6 2109.39  5032.1 2112.35  5040.1 2113.31  5089.7 2117.02
  5196.1 2118.49  5203.3 2119.34  5232.1 2119.80  5238.6 2120.83  5246.6 2121.34
  5253.0 2121.30  5267.4 2122.37  5281.8 2122.83  5302.6 2124.64  5324.2 2125.23
#Mann=3,-1,0
  4749.1    0.07       0  4990.8    0.05       0  4996.8    0.07       0
Bank Sta=4990.8,4996.8
Exp/Cntr=0.3,0.1

Type RM Length L Ch R = 1,4211,422,422,422
BEGIN DESCRIPTION:
Stream0183 9.0
END DESCRIPTION:
XS GIS Cut Line= 3
      1813525.00     13955875.01      1813475.00     13955975.00
      1813374.98     13956225.04
#Sta/Elev= 30
  4883.9 2122.80  4914.6 2120.86  4951.0 2116.22  4959.4 2114.28  4964.9 2112.37
  4973.3 2110.53  4981.7 2107.57  4987.3 2106.10  4992.9 2105.08  5002.1 2105.07
  5002.6 2104.57  5007.7 2104.57  5008.2 2105.07  5017.2 2106.04  5034.7 2106.86
  5040.1 2106.07  5049.5 2106.85  5081.9 2106.79  5103.4 2108.39  5118.2 2109.86
  5124.9 2110.95  5135.7 2111.81  5142.4 2113.37  5147.8 2113.82  5178.8 2118.02
  5196.3 2119.94  5201.7 2119.91  5211.1 2119.25  5225.9 2119.32  5265.0 2120.39
#Mann=3,-1,0
  4883.9    0.07       0  5002.1    0.05       0  5008.2    0.07       0
Bank Sta=5002.1,5008.2
Exp/Cntr=0.3,0.1

Type RM Length L Ch R = 1,3789,499,499,499
BEGIN DESCRIPTION:
Stream0183 8.0
END DESCRIPTION:
XS GIS Cut Line= 3
      1813125.00     13955674.99      1813125.00     13955775.00
      1813125.00     13956124.99
#Sta/Elev= 30
  4900.4 2120.54  4910.4 2120.32  4950.4 2117.75  4960.4 2115.36  4970.4 2112.29
  4980.4 2108.81  4990.4 2105.77  4997.9 2102.54  5017.3 2102.27  5017.8 2101.77
  5023.0 2101.77  5023.5 2102.27  5030.4 2102.44  5040.4 2102.34  5070.4 2104.27
  5090.4 2104.60  5100.4 2104.26  5110.4 2104.93  5120.4 2105.32  5150.4 2107.86
  5180.4 2109.64  5220.4 2110.71  5240.4 2111.56  5260.4 2112.47  5280.4 2113.79
  5310.4 2115.05  5330.4 2116.35  5340.4 2116.38  5347.9 2116.97  5350.4 2116.97
#Mann=3,-1,0
  4900.4    0.07       0  5017.3    0.05       0  5023.5    0.07       0
Bank Sta=5017.3,5023.5
Exp/Cntr=0.3,0.1

Type RM Length L Ch R = 1,3290,452,452,452
BEGIN DESCRIPTION:
Stream0183 7.0
END DESCRIPTION:
XS GIS Cut Line= 3
      1812724.99     13955425.05      1812625.00     13955775.00
      1812524.99     13956125.04
#Sta/Elev= 30
  4640.2 2114.39  4701.7 2111.74  4763.7 2108.95  4768.9 2109.89  4775.4 2108.58
  4802.7 2106.18  4807.9 2106.66  4817.0 2106.15  4836.5 2103.20  4841.7 2104.24
  4858.6 2101.90  4900.2 2102.96  4914.5 2101.92  4941.8 2101.57  4948.3 2098.99
  4962.6 2098.66  4973.0 2099.32  4979.0 2098.15  4979.5 2097.65  4985.2 2098.15
  5005.6 2098.22  5021.1 2099.51  5026.3 2099.06  5045.8 2101.55  5060.1 2101.79
  5093.9 2104.83  5244.7 2110.74  5264.2 2112.61  5312.3 2120.01  5368.2 2123.29
#Mann=5,-1,0
  4640.2    0.07       0  4701.7     0.1       0  4979.0    0.05       0
  4985.2     0.1       0  5005.6    0.07       0
Bank Sta=4979,4985.2
Exp/Cntr=0.3,0.1

Type RM Length L Ch R = 1,2838,468,468,468
BEGIN DESCRIPTION:
Stream0183 6.0
END DESCRIPTION:
XS GIS Cut Line= 3
      1812625.01     13955424.99      1812225.00     13955825.00
      1812225.00     13955925.01
#Sta/Elev= 30
  4438.4 2113.58  4466.9 2112.11  4480.8 2111.86  4579.8 2106.43  4606.6 2105.50
  4650.7 2103.13  4707.1 2100.59  4728.1 2100.20  4749.5 2099.42  4792.0 2098.90
  4806.1 2099.19  4834.4 2101.56  4862.7 2100.65  4876.8 2099.72  4919.2 2099.14
  4933.4 2099.36  4947.5 2099.01  4961.7 2097.63  4972.6 2094.67  4973.1 2094.17
  4978.5 2094.17  4979.0 2094.67  4990.0 2094.86  5000.6 2102.69  5006.6 2102.69
  5014.1 2107.93  5024.1 2111.37  5034.1 2113.19  5054.1 2115.72  5104.1 2119.64
#Mann=7,-1,0
  4438.4    0.07       0  4466.9     0.1       0  4606.6    0.07       0
  4650.7     0.1       0  4728.1    0.07       0  4972.6    0.05       0
  4979.0    0.07       0
Bank Sta=4972.6,4979
Exp/Cntr=0.3,0.1

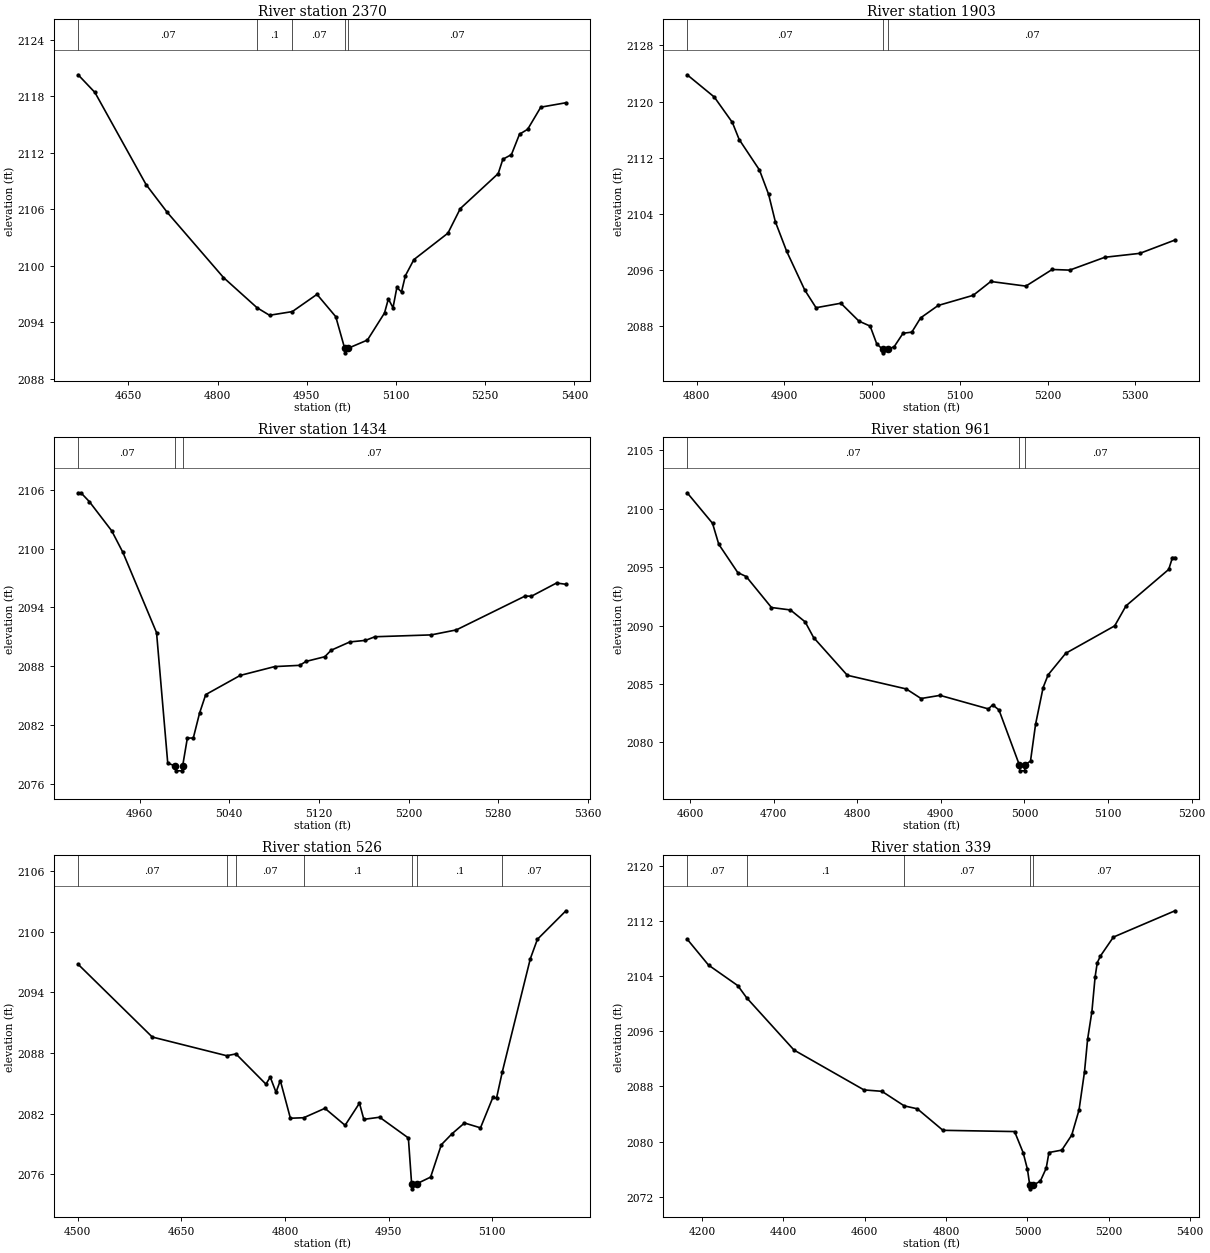
Type RM Length L Ch R = 1,2370,467,467,467
BEGIN DESCRIPTION:
Stream0183 5.0
END DESCRIPTION:
XS GIS Cut Line= 3
      1812275.00     13955075.00      1812025.00     13955425.00
      1811775.02     13955724.98
#Sta/Elev= 30
  4565.3 2120.28  4593.6 2118.40  4679.6 2108.62  4715.2 2105.67  4809.8 2098.75
  4866.3 2095.54  4887.3 2094.74  4925.6 2095.13  4967.1 2096.96  4998.7 2094.59
  5013.6 2091.25  5014.1 2090.75  5020.1 2091.25  5052.0 2092.11  5080.7 2094.98
  5087.2 2096.48  5095.0 2095.54  5101.5 2097.69  5109.3 2097.22  5115.8 2098.94
  5130.1 2100.65  5187.4 2103.46  5208.2 2106.07  5272.0 2109.79  5279.8 2111.31
  5294.2 2111.80  5307.8 2113.97  5321.5 2114.49  5343.6 2116.84  5385.9 2117.31
#Mann=5,-1,0
  4565.3    0.07       0  4866.3     0.1       0  4925.6    0.07       0
  5013.6    0.05       0  5020.1    0.07       0
Bank Sta=5013.6,5020.1
Exp/Cntr=0.3,0.1

Type RM Length L Ch R = 1,1903,469,469,469
BEGIN DESCRIPTION:
Stream0183 4.0
END DESCRIPTION:
XS GIS Cut Line= 3
      1811775.00     13954875.02      1811725.00     13955075.00
      1811725.00     13955424.96
#Sta/Elev= 30
  4789.1 2123.82  4820.0 2120.65  4840.6 2117.03  4848.4 2114.59  4871.5 2110.25
  4881.9 2106.79  4889.6 2102.88  4902.5 2098.67  4923.1 2093.15  4936.0 2090.62
  4964.3 2091.26  4984.9 2088.71  4997.7 2088.00  5005.2 2085.47  5011.9 2084.69
  5012.4 2084.19  5018.5 2084.69  5025.2 2085.09  5035.2 2086.98  5045.2 2087.14
  5055.2 2089.17  5075.2 2090.94  5115.2 2092.39  5135.2 2094.36  5175.2 2093.70
  5205.2 2096.07  5225.2 2095.98  5265.2 2097.81  5305.2 2098.37  5345.2 2100.27
#Mann=3,-1,0
  4789.1    0.07       0  5011.9    0.05       0  5018.5    0.07       0
Bank Sta=5011.9,5018.5
Exp/Cntr=0.3,0.1

Type RM Length L Ch R = 1,1434,473,473,473
BEGIN DESCRIPTION:
Stream0183 3.0
END DESCRIPTION:
XS GIS Cut Line= 3
      1811325.00     13954975.03      1811325.00     13955075.00
      1811475.01     13955375.01
#Sta/Elev= 30
  4905.1 2105.72  4907.6 2105.72  4915.1 2104.82  4935.1 2101.83  4945.1 2099.62
  4975.1 2091.43  4985.1 2078.09  4991.8 2077.81  4992.3 2077.31  4997.9 2077.31
  4998.4 2077.81  5002.6 2080.66  5007.9 2080.66  5013.5 2083.21  5019.0 2085.10
  5049.8 2087.06  5080.5 2087.96  5102.9 2088.09  5108.5 2088.49  5125.3 2088.97
  5130.9 2089.63  5147.6 2090.48  5161.6 2090.64  5170.0 2091.01  5220.3 2091.20
  5242.7 2091.71  5304.1 2095.17  5309.7 2095.15  5332.1 2096.50  5340.5 2096.37
#Mann=3,-1,0
  4905.1    0.07       0  4991.8    0.05       0  4998.4    0.07       0
Bank Sta=4991.8,4998.4
Exp/Cntr=0.3,0.1

Type RM Length L Ch R = 1,961,435,435,435
BEGIN DESCRIPTION:
Stream0183 2.0
END DESCRIPTION:
XS GIS Cut Line= 3
      1811025.00     13954974.98      1810975.00     13955375.00
      1811074.99     13955524.99
#Sta/Elev= 30
  4596.6 2101.36  4626.9 2098.75  4634.4 2096.95  4657.1 2094.53  4667.2 2094.19
  4697.4 2091.54  4720.1 2091.33  4737.7 2090.31  4747.8 2088.97  4788.1 2085.74
  4858.6 2084.57  4876.3 2083.75  4899.0 2084.02  4956.9 2082.86  4961.9 2083.21
  4969.5 2082.77  4993.9 2078.06  4994.4 2077.56  5000.1 2077.56  5000.6 2078.06
  5007.2 2078.40  5013.3 2081.56  5022.3 2084.69  5028.3 2085.78  5049.3 2087.62
  5107.9 2089.97  5121.4 2091.68  5172.5 2094.80  5177.0 2095.82  5180.0 2095.82
#Mann=3,-1,0
  4596.6    0.07       0  4993.9    0.05       0  5000.6    0.07       0
Bank Sta=4993.9,5000.6
Exp/Cntr=0.3,0.1

Type RM Length L Ch R = 1,526,187,187,187
BEGIN DESCRIPTION:
Stream0183 1.0
END DESCRIPTION:
XS GIS Cut Line= 3
      1810875.01     13954974.99      1810575.00     13955375.00
      1810524.99     13955575.03
#Sta/Elev= 30
  4500.4 2096.78  4607.7 2089.59  4715.5 2087.74  4728.9 2087.92  4772.3 2084.93
  4778.5 2085.63  4786.9 2084.13  4793.1 2085.29  4807.7 2081.56  4827.0 2081.61
  4857.7 2082.54  4886.9 2080.86  4907.7 2083.05  4914.0 2081.45  4936.9 2081.66
  4978.5 2079.61  4983.2 2075.08  4983.7 2074.58  4990.6 2075.08  5010.7 2075.74
  5026.2 2078.94  5041.6 2080.02  5059.7 2081.09  5082.9 2080.61  5100.9 2083.63
  5106.1 2083.54  5114.6 2086.18  5155.0 2097.32  5165.3 2099.25  5206.6 2102.07
#Mann=7,-1,0
  4500.4    0.07       0  4715.5     0.1       0  4728.9    0.07       0
  4827.0     0.1       0  4983.2    0.05       0  4990.6     0.1       0
  5114.6    0.07       0
Bank Sta=4983.2,4990.6
Exp/Cntr=0.3,0.1

Type RM Length L Ch R = 1,339,292,292,292
BEGIN DESCRIPTION:
Stream0183 0.0
END DESCRIPTION:
XS GIS Cut Line= 3
      1810837.36     13954613.65      1810448.48     13955194.70
      1810287.78     13955668.52
#Sta/Elev= 30
  4163.2 2109.36  4215.7 2105.60  4287.7 2102.62  4309.7 2100.84  4425.8 2093.28
  4598.0 2087.49  4642.0 2087.29  4696.8 2085.18  4729.1 2084.75  4792.1 2081.63
  4968.3 2081.45  4989.4 2078.38  5000.0 2075.95  5005.6 2073.64  5006.1 2073.14
  5013.0 2073.64  5031.6 2074.26  5046.0 2076.13  5052.8 2078.41  5084.4 2078.76
  5108.8 2080.94  5126.7 2084.57  5140.2 2090.12  5147.8 2094.83  5158.4 2098.86
  5166.3 2103.90  5171.6 2105.95  5179.5 2106.93  5211.2 2109.66  5362.7 2113.48
#Mann=5,-1,0
  4163.2    0.07       0  4309.7     0.1       0  4696.8    0.07       0
  5005.6    0.05       0  5013.0    0.07       0
Bank Sta=5005.6,5013
Exp/Cntr=0.3,0.1

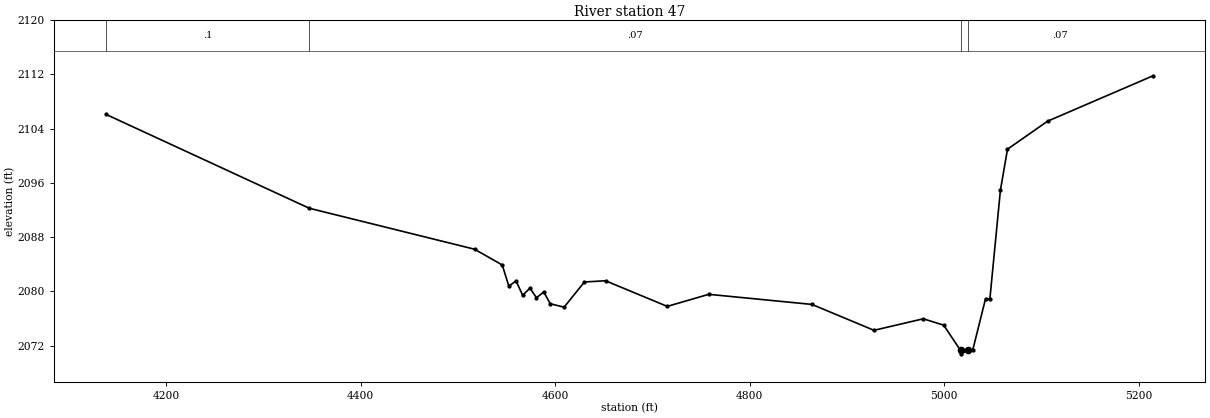
Type RM Length L Ch R = 1,47,0,0,0
BEGIN DESCRIPTION:
Stream0183 T
END DESCRIPTION:
XS GIS Cut Line= 4
      1810724.37     13954609.36      1810207.85     13955186.64
      1810131.90     13955297.31      1810095.26     13955461.12
#Sta/Elev= 30
  4138.2 2106.11  4347.1 2092.27  4517.2 2086.22  4545.6 2083.90  4552.4 2080.78
  4559.8 2081.54  4566.6 2079.43  4574.1 2080.48  4580.8 2079.07  4588.3 2079.91
  4595.0 2078.18  4609.2 2077.67  4630.1 2081.39  4651.8 2081.57  4715.3 2077.79
  4758.0 2079.57  4864.1 2078.08  4927.9 2074.26  4978.6 2075.96  4999.6 2075.02
  5016.9 2071.29  5017.4 2070.79  5024.3 2071.29  5029.4 2071.31  5042.6 2078.91
  5047.1 2078.91  5057.9 2094.92  5065.2 2100.98  5106.4 2105.11  5214.9 2111.81
#Mann=4,-1,0
  4138.2     0.1       0  4347.1    0.07       0  5016.9    0.05       0
  5024.3    0.07       0
Bank Sta=5016.9,5024.3
Exp/Cntr=0.3,0.1

Chan Stop Cuts=-1