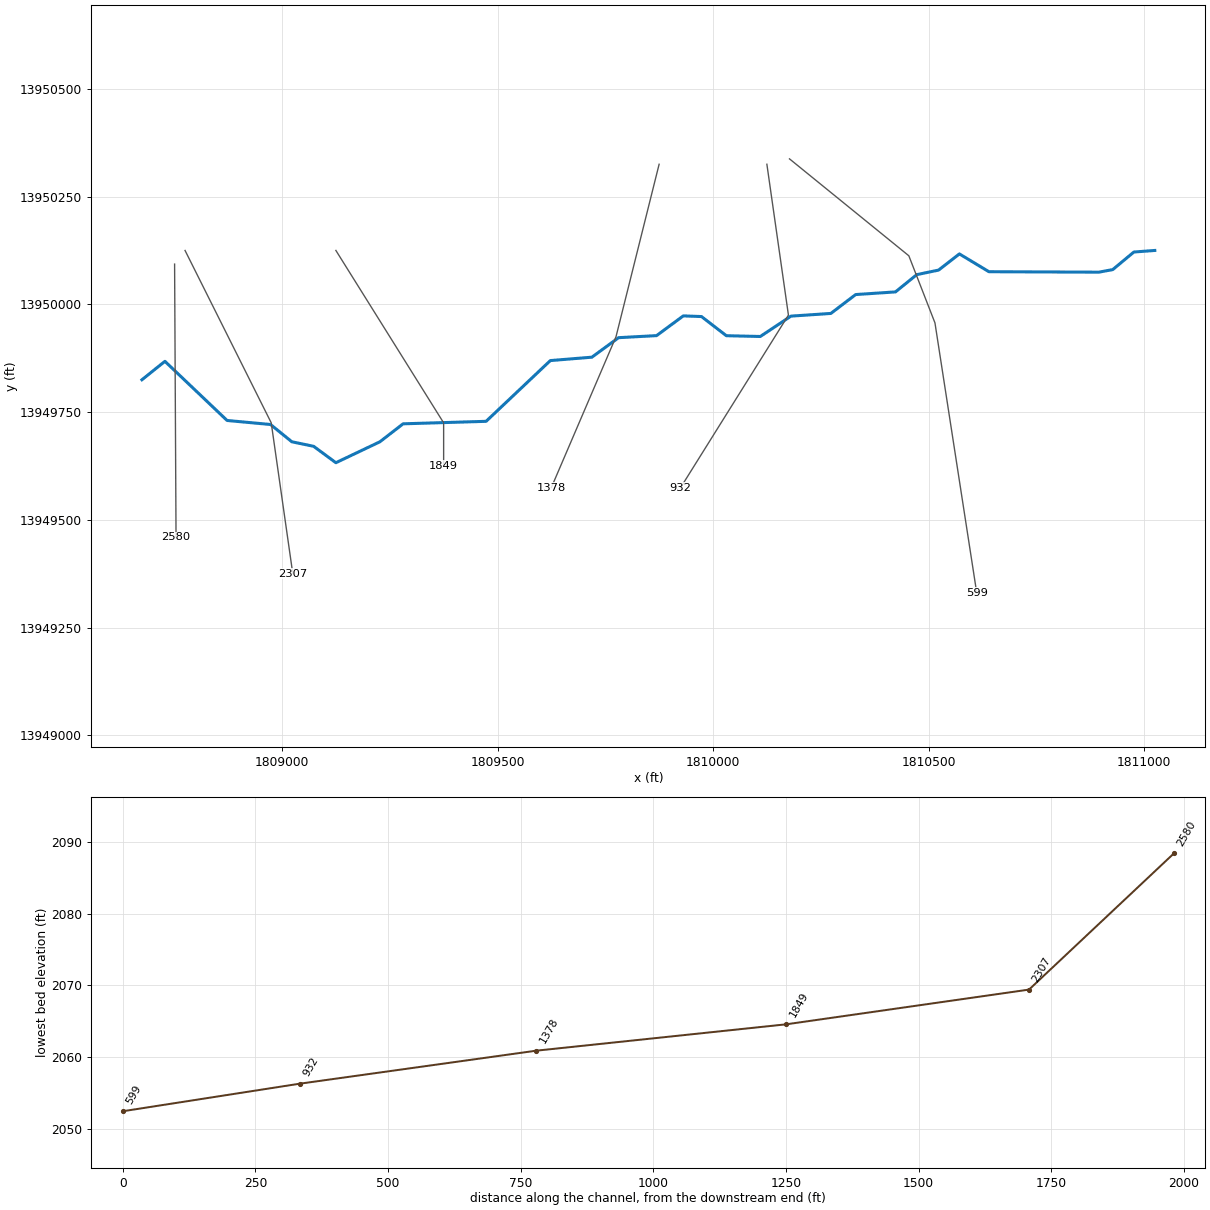
--- Stream0184.prj (project) ---

Proj Title=Stream0184 Base Level Engineering
Current Plan=p01
Default Exp/Contr=0.3,0.1
English Units
Geom File=g01
Flow File=f01
Plan File=p01
BEGIN DESCRIPTION:
Stream0184
END DESCRIPTION:

--- Stream0184.p01 (plan) ---

Plan Title=Multiple Run
Short Identifier=Multiple
Geom File=g01
Flow File=f01
Subcritical Flow
K Sum by GR= 0
Std Step Tol= 0.01
Critical Tol= 0.01
Num of Std Step Trials= 20
Max Error Tol= 0.3
Flow Tol Ratio= 0.001
Split Flow NTrial= 30
Split Flow Tol= 0.02
Split Flow Ratio= 0.02
Log Output Level= 0
Friction Slope Method= 1
Unsteady Friction Slope Method= 2
Unsteady Bridges Friction Slope Method= 1
Parabolic Critical Depth
Global Vel Dist=  1 , 1 , 1
Global Log Level= 0
CheckData=True
Encroach Param= -1, 0, 0, 0
BEGIN DESCRIPTION:
Multiple Run
END DESCRIPTION:

--- Stream0184.f01 (steady flow) ---

Flow Title=Multiple
Number of Profiles=7
Profile Names=10-year,25-year,50-year,1pct_min,100-year,1pct_plu,500-year
River Rch & RM= Stream0184,Reach-1,2580
    1146    1961    2737    1844    3679    7341    6575
Boundary for River Rch & Prof#=Stream0184,Reach-1,1
Up Type=0
Dn Type=3
Dn Slope=0.005
Boundary for River Rch & Prof#=Stream0184,Reach-1,2
Up Type=0
Dn Type=3
Dn Slope=0.005
Boundary for River Rch & Prof#=Stream0184,Reach-1,3
Up Type=0
Dn Type=3
Dn Slope=0.005
Boundary for River Rch & Prof#=Stream0184,Reach-1,4
Up Type=0
Dn Type=3
Dn Slope=0.005
Boundary for River Rch & Prof#=Stream0184,Reach-1,5
Up Type=0
Dn Type=3
Dn Slope=0.005
Boundary for River Rch & Prof#=Stream0184,Reach-1,6
Up Type=0
Dn Type=3
Dn Slope=0.005
Boundary for River Rch & Prof#=Stream0184,Reach-1,7
Up Type=0
Dn Type=3
Dn Slope=0.005

--- Stream0184.g01 (geometry) ---

Geom Title=Existing Conditions

River Reach=Stream0184,Reach-1
Reach XY= 30
      1808675.00     13949825.00      1808728.33     13949867.75
      1808872.57     13949730.52      1808973.41     13949721.17
      1809022.83     13949681.09      1809073.36     13949670.58
      1809125.00     13949632.50      1809227.17     13949681.09
      1809280.93     13949722.76      1809473.54     13949728.54
      1809622.57     13949869.48      1809719.02     13949877.36
      1809780.97     13949922.65      1809869.03     13949927.38
      1809931.12     13949973.18      1809973.27     13949971.62
      1810030.97     13949927.19      1810109.73     13949925.38
      1810180.97     13949972.64      1810273.40     13949978.85
      1810330.97     13950022.65      1810423.42     13950028.83
      1810472.83     13950068.91      1810523.36     13950079.42
      1810571.68     13950116.96      1810640.16     13950075.66
      1810895.16     13950074.62      1810927.42     13950080.53
      1810976.51     13950121.35      1811025.00     13950125.00

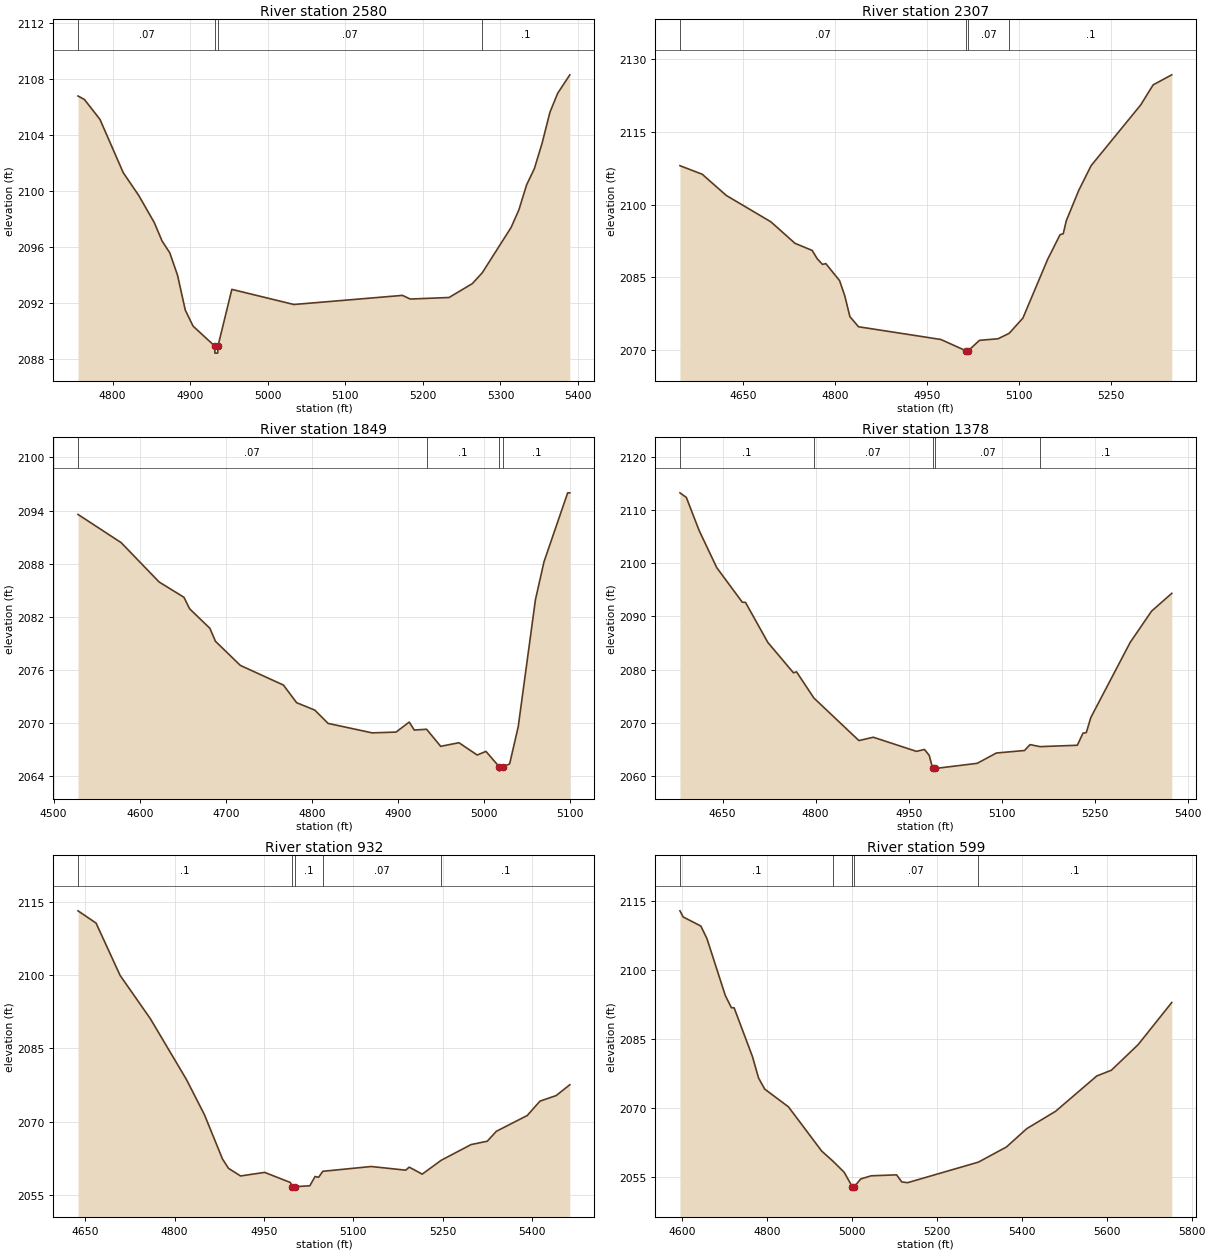
Type RM Length L Ch R = 1,2580,273,273,273
BEGIN DESCRIPTION:
Stream0184 5.0
END DESCRIPTION:
XS GIS Cut Line= 2
      1808750.79     13950093.33      1808754.12     13949459.34
#Sta/Elev= 30
  4755.4 2106.78  4763.7 2106.53  4783.7 2105.11  4813.7 2101.31  4833.7 2099.68
  4853.7 2097.75  4863.7 2096.44  4873.7 2095.59  4883.7 2093.99  4893.7 2091.50
  4903.7 2090.36  4931.7 2088.93  4931.9 2088.43  4935.5 2088.43  4935.8 2088.93
  4953.7 2092.98  5033.7 2091.90  5173.7 2092.55  5183.7 2092.29  5233.7 2092.40
  5263.7 2093.39  5276.6 2094.17  5313.7 2097.40  5323.7 2098.65  5333.7 2100.44
  5343.7 2101.60  5353.7 2103.42  5363.7 2105.61  5373.7 2106.97  5389.4 2108.29
#Mann=4,-1,0
  4755.4    0.07       0  4931.7    0.05       0  4935.8    0.07       0
  5276.6     0.1       0
Bank Sta=4931.7,4935.8
Exp/Cntr=0.3,0.1

Type RM Length L Ch R = 1,2307,458,458,458
BEGIN DESCRIPTION:
Stream0184 4.0
END DESCRIPTION:
XS GIS Cut Line= 3
      1808775.02     13950124.97      1808975.00     13949725.00
      1809025.00     13949375.03
#Sta/Elev= 30
  4547.8 2108.01  4584.1 2106.25  4623.2 2101.89  4695.9 2096.45  4735.0 2092.04
  4763.0 2090.57  4771.4 2088.84  4779.8 2087.69  4785.3 2087.85  4807.7 2084.35
  4816.1 2081.24  4824.5 2076.93  4838.5 2074.85  4972.6 2072.23  5013.1 2069.92
  5013.4 2069.42  5017.2 2069.92  5035.4 2072.05  5065.7 2072.38  5083.7 2073.49
  5106.1 2076.63  5146.5 2088.75  5166.7 2093.82  5171.8 2094.01  5176.8 2096.69
  5197.0 2102.91  5217.2 2108.02  5298.0 2120.54  5318.2 2124.66  5348.5 2126.72
#Mann=4,-1,0
  4547.8    0.07       0  5013.1    0.05       0  5017.2    0.07       0
  5083.7     0.1       0
Bank Sta=5013.1,5017.2
Exp/Cntr=0.3,0.1

Type RM Length L Ch R = 1,1849,471,471,471
BEGIN DESCRIPTION:
Stream0184 3.0
END DESCRIPTION:
XS GIS Cut Line= 3
      1809125.01     13950124.99      1809375.00     13949725.00
      1809375.00     13949624.99
#Sta/Elev= 30
  4528.3 2093.56  4578.4 2090.38  4622.6 2085.93  4651.5 2084.20  4658.0 2082.91
  4681.6 2080.70  4688.1 2079.23  4717.0 2076.51  4767.1 2074.29  4782.4 2072.30
  4803.6 2071.46  4819.0 2069.96  4870.3 2068.89  4898.0 2068.98  4913.3 2070.11
  4919.2 2069.21  4933.5 2069.30  4949.9 2067.37  4971.1 2067.78  4992.3 2066.39
  5002.5 2066.80  5017.9 2065.07  5018.2 2064.57  5022.0 2065.07  5030.0 2065.38
  5040.0 2069.58  5060.0 2083.92  5070.0 2088.22  5097.5 2096.00  5100.0 2096.00
#Mann=4,-1,0
  4528.3    0.07       0  4933.5     0.1       0  5017.9    0.05       0
  5022.0     0.1       0
Bank Sta=5017.9,5022
Exp/Cntr=0.3,0.1

Type RM Length L Ch R = 1,1378,446,446,446
BEGIN DESCRIPTION:
Stream0184 2.0
END DESCRIPTION:
XS GIS Cut Line= 3
      1809875.00     13950325.00      1809775.00     13949925.00
      1809625.00     13949575.00
#Sta/Elev= 30
  4581.2 2113.27  4591.5 2112.41  4612.1 2106.19  4640.5 2099.20  4681.7 2092.69
  4686.9 2092.65  4722.9 2085.12  4764.2 2079.40  4769.3 2079.57  4797.2 2074.65
  4869.8 2066.64  4893.0 2067.27  4962.6 2064.61  4975.5 2064.97  4983.2 2063.85
  4988.8 2061.39  4989.1 2060.89  4993.0 2061.39  5060.6 2062.36  5091.4 2064.30
  5136.8 2064.77  5145.8 2065.88  5161.9 2065.50  5222.0 2065.76  5231.1 2068.03
  5236.5 2068.15  5243.7 2070.97  5307.2 2085.11  5341.7 2091.00  5374.3 2094.35
#Mann=5,-1,0
  4581.2     0.1       0  4797.2    0.07       0  4988.8    0.05       0
  4993.0    0.07       0  5161.9     0.1       0
Bank Sta=4988.8,4993
Exp/Cntr=0.3,0.1

Type RM Length L Ch R = 1,932,333,333,333
BEGIN DESCRIPTION:
Stream0184 1.0
END DESCRIPTION:
XS GIS Cut Line= 3
      1810125.00     13950325.03      1810175.00     13949975.00
      1809924.99     13949574.98
#Sta/Elev= 30
  4637.9 2113.11  4668.2 2110.61  4708.6 2099.91  4759.1 2091.12  4819.8 2078.68
  4850.1 2071.47  4880.4 2062.42  4890.5 2060.52  4910.7 2058.97  4951.1 2059.70
  4994.4 2057.63  4997.0 2056.78  4997.3 2056.28  5001.2 2056.78  5026.9 2056.96
  5035.7 2058.86  5041.6 2058.69  5048.7 2059.92  5130.0 2060.90  5187.8 2060.15
  5193.7 2060.77  5215.5 2059.34  5247.2 2062.16  5297.5 2065.38  5324.6 2066.06
  5339.9 2068.09  5391.8 2071.32  5413.1 2074.25  5440.2 2075.38  5463.2 2077.60
#Mann=5,-1,0
  4637.9     0.1       0  4997.0    0.05       0  5001.2     0.1       0
  5048.7    0.07       0  5247.2     0.1       0
Bank Sta=4997,5001.2
Exp/Cntr=0.3,0.1

Type RM Length L Ch R = 1,599,0,0,0
BEGIN DESCRIPTION:
Stream0184 0.0
END DESCRIPTION:
XS GIS Cut Line= 4
      1810177.48     13950337.50      1810454.36     13950112.66
      1810515.00     13949956.92      1810611.92     13949330.58
#Sta/Elev= 30
  4595.6 2112.81  4603.2 2111.48  4644.8 2109.51  4659.2 2106.78  4702.3 2094.46
  4716.7 2091.79  4723.1 2091.78  4766.2 2081.21  4780.6 2076.56  4795.0 2074.15
  4851.0 2070.29  4929.3 2060.69  4955.4 2058.53  4982.0 2056.12  5001.3 2052.94
  5001.6 2052.44  5005.5 2052.94  5021.2 2054.65  5045.7 2055.33  5105.5 2055.54
  5117.8 2054.00  5131.5 2053.84  5298.1 2058.30  5364.2 2061.59  5411.7 2065.55
  5479.8 2069.33  5576.7 2076.99  5611.0 2078.23  5674.0 2083.78  5753.2 2092.93
#Mann=5,-1,0
  4595.6     0.1       0  4955.4    0.07       0  5001.3    0.05       0
  5005.5    0.07       0  5298.1     0.1       0
Bank Sta=5001.3,5005.5
Exp/Cntr=0.3,0.1

Chan Stop Cuts=-1