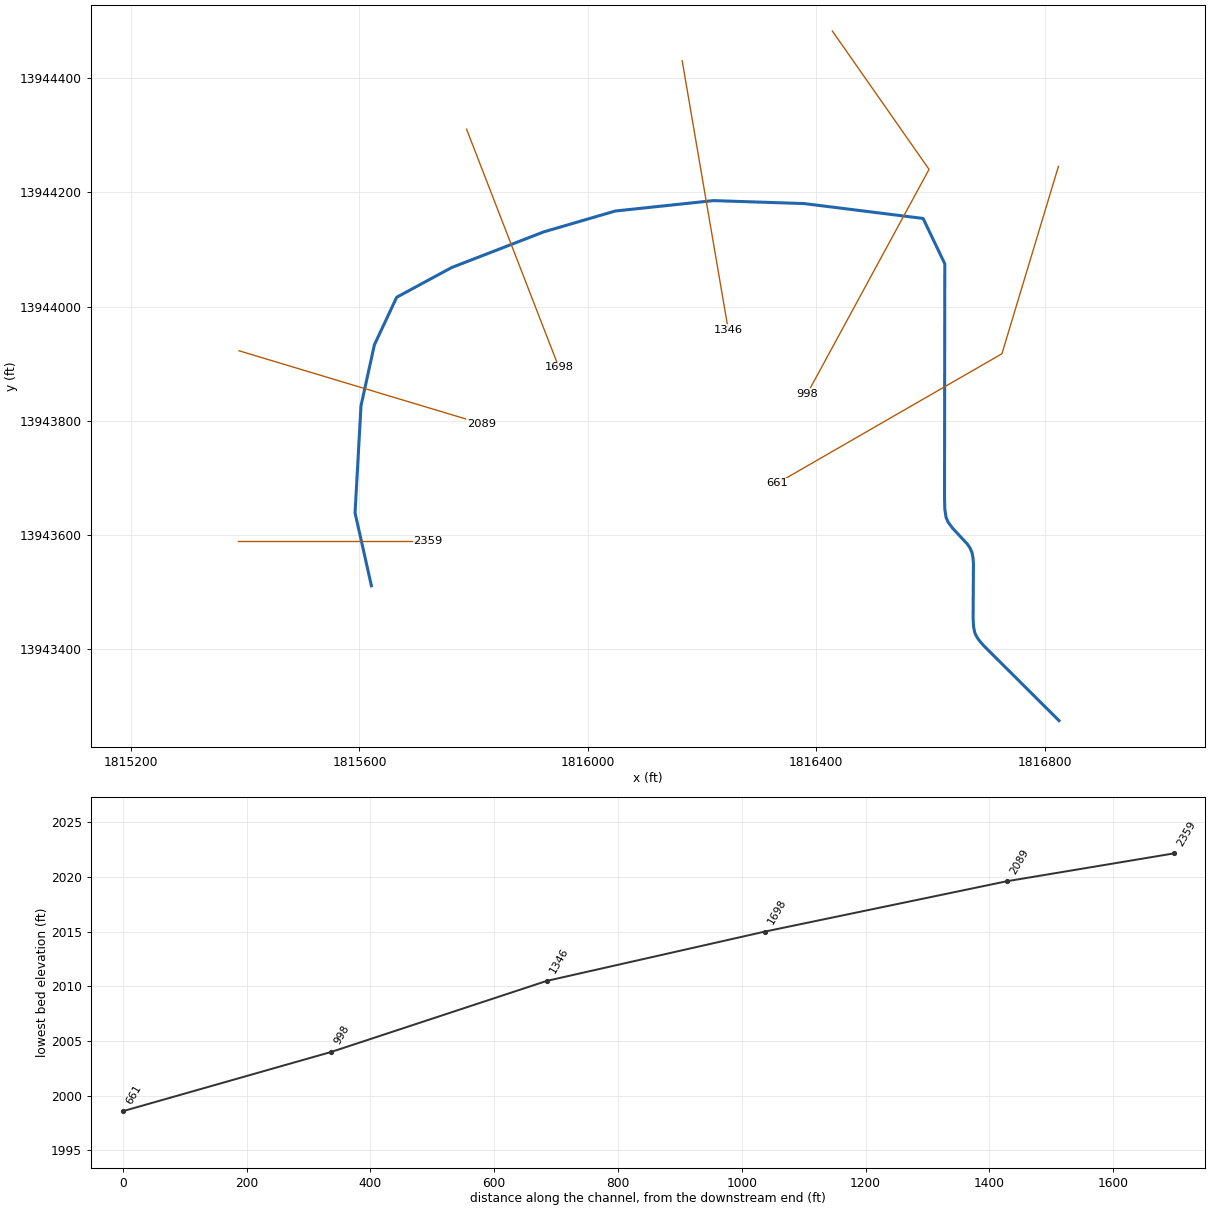
--- Stream0186.prj (project) ---

Proj Title=Stream0186 Base Level Engineering
Current Plan=p01
Default Exp/Contr=0.3,0.1
English Units
Geom File=g01
Flow File=f01
Plan File=p01
BEGIN DESCRIPTION:
Stream0186
END DESCRIPTION:

--- Stream0186.p01 (plan) ---

Plan Title=Multiple Run
Short Identifier=Multiple
Geom File=g01
Flow File=f01
Subcritical Flow
K Sum by GR= 0
Std Step Tol= 0.01
Critical Tol= 0.01
Num of Std Step Trials= 20
Max Error Tol= 0.3
Flow Tol Ratio= 0.001
Split Flow NTrial= 30
Split Flow Tol= 0.02
Split Flow Ratio= 0.02
Log Output Level= 0
Friction Slope Method= 1
Unsteady Friction Slope Method= 2
Unsteady Bridges Friction Slope Method= 1
Parabolic Critical Depth
Global Vel Dist=  1 , 1 , 1
Global Log Level= 0
CheckData=True
Encroach Param= -1, 0, 0, 0
BEGIN DESCRIPTION:
Multiple Run
END DESCRIPTION:

--- Stream0186.f01 (steady flow) ---

Flow Title=Multiple
Number of Profiles=7
Profile Names=10-year,25-year,50-year,1pct_min,100-year,1pct_plu,500-year
River Rch & RM= Stream0186,Reach-1,2359
    1433    2484    3496    2373    4735    9447    8595
Boundary for River Rch & Prof#=Stream0186,Reach-1,1
Up Type=0
Dn Type=3
Dn Slope=0.005
Boundary for River Rch & Prof#=Stream0186,Reach-1,2
Up Type=0
Dn Type=3
Dn Slope=0.005
Boundary for River Rch & Prof#=Stream0186,Reach-1,3
Up Type=0
Dn Type=3
Dn Slope=0.005
Boundary for River Rch & Prof#=Stream0186,Reach-1,4
Up Type=0
Dn Type=3
Dn Slope=0.005
Boundary for River Rch & Prof#=Stream0186,Reach-1,5
Up Type=0
Dn Type=3
Dn Slope=0.005
Boundary for River Rch & Prof#=Stream0186,Reach-1,6
Up Type=0
Dn Type=3
Dn Slope=0.005
Boundary for River Rch & Prof#=Stream0186,Reach-1,7
Up Type=0
Dn Type=3
Dn Slope=0.005

--- Stream0186.g01 (geometry) ---

Geom Title=Existing Conditions

River Reach=Stream0186,Reach-1
Reach XY= 30
      1815620.87     13943511.22      1815592.23     13943638.82
      1815602.64     13943826.32      1815626.08     13943933.09
      1815665.14     13944016.43      1815761.50     13944068.51
      1815922.96     13944131.01      1816047.96     13944167.47
      1816219.83     13944185.70      1816378.69     13944180.49
      1816587.02     13944154.45      1816625.00     13944075.00
      1816624.55     13943664.81      1816625.07     13943645.03
      1816627.26     13943630.94      1816630.75     13943622.67
      1816638.79     13943611.86      1816664.14     13943584.64
      1816669.25     13943577.33      1816672.73     13943569.06
      1816674.46     13943559.78      1816675.18     13943550.07
      1816674.60     13943454.83      1816675.40     13943440.16
      1816677.06     13943430.85      1816678.54     13943426.47
      1816682.81     13943418.81      1816688.37     13943411.68
      1816694.60     13943404.83      1816825.00     13943275.00

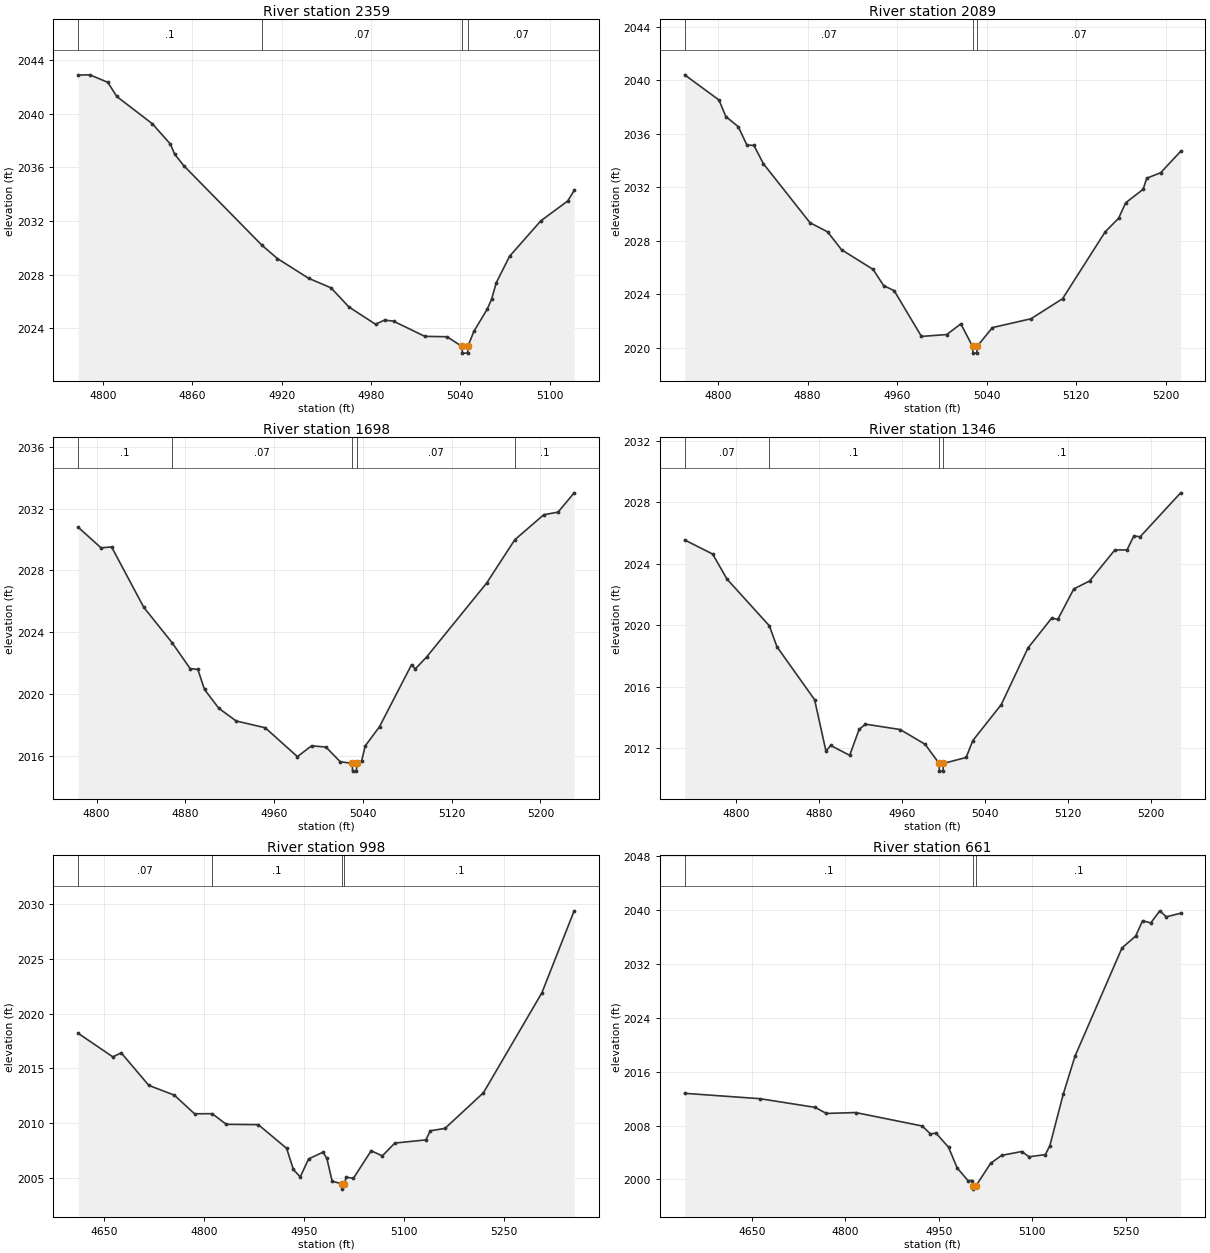
Type RM Length L Ch R = 1,2359,270,270,270
BEGIN DESCRIPTION:
Stream0186 6.0
END DESCRIPTION:
XS GIS Cut Line= 2
      1815386.53     13943589.34      1815719.83     13943589.34
#Sta/Elev= 30
  4783.2 2042.86  4791.0 2042.88  4803.1 2042.32  4809.1 2041.27  4833.1 2039.23
  4845.1 2037.73  4848.0 2036.98  4854.1 2036.12  4906.6 2030.20  4917.1 2029.20
  4938.1 2027.73  4953.1 2027.02  4965.1 2025.60  4983.0 2024.31  4989.1 2024.62
  4995.1 2024.54  5016.1 2023.41  5031.1 2023.38  5041.1 2022.66  5041.4 2022.16
  5044.9 2022.16  5045.1 2022.66  5049.1 2023.78  5058.1 2025.44  5061.1 2026.20
  5064.1 2027.39  5073.1 2029.37  5094.1 2032.01  5112.2 2033.49  5116.5 2034.27
#Mann=4,-1,0
  4783.2     0.1       0  4906.6    0.07       0  5041.1    0.05       0
  5045.1    0.07       0
Bank Sta=5041.1,5045.1
Exp/Cntr=0.3,0.1

Type RM Length L Ch R = 1,2089,391,391,391
BEGIN DESCRIPTION:
Stream0186 5.0
END DESCRIPTION:
XS GIS Cut Line= 2
      1815389.10     13943922.68      1815813.54     13943795.09
#Sta/Elev= 30
  4770.1 2040.42  4800.7 2038.54  4806.9 2037.30  4818.0 2036.54  4825.7 2035.17
  4832.0 2035.14  4840.4 2033.78  4882.1 2029.36  4897.8 2028.68  4910.3 2027.34
  4938.5 2025.87  4947.9 2024.66  4957.3 2024.28  4981.7 2020.86  5004.3 2021.00
  5016.9 2021.80  5027.4 2020.11  5027.7 2019.61  5031.2 2019.61  5031.4 2020.11
  5045.1 2021.52  5079.6 2022.18  5107.8 2023.68  5145.8 2028.67  5157.9 2029.70
  5164.2 2030.85  5179.8 2031.86  5183.0 2032.69  5195.5 2033.10  5213.3 2034.70
#Mann=3,-1,0
  4770.1    0.07       0  5027.4    0.05       0  5031.4    0.07       0
Bank Sta=5027.4,5031.4
Exp/Cntr=0.3,0.1

Type RM Length L Ch R = 1,1698,352,352,352
BEGIN DESCRIPTION:
Stream0186 3.0
END DESCRIPTION:
XS GIS Cut Line= 2
      1815787.52     13944310.74      1815949.00     13943894.03
#Sta/Elev= 30
  4783.5 2030.80  4804.0 2029.47  4813.6 2029.52  4842.6 2025.61  4868.2 2023.31
  4884.4 2021.64  4891.3 2021.59  4897.3 2020.29  4910.2 2019.07  4925.8 2018.25
  4952.0 2017.81  4981.0 2015.94  4993.8 2016.64  5006.7 2016.56  5019.6 2015.61
  5030.5 2015.50  5030.7 2015.00  5034.2 2015.00  5034.5 2015.50  5038.9 2015.66
  5042.1 2016.63  5055.0 2017.88  5083.9 2021.90  5087.2 2021.62  5097.4 2022.39
  5151.5 2027.18  5176.9 2029.99  5203.0 2031.61  5215.9 2031.78  5230.4 2033.03
#Mann=5,-1,0
  4783.5     0.1       0  4868.2    0.07       0  5030.5    0.05       0
  5034.5    0.07       0  5176.9     0.1       0
Bank Sta=5030.5,5034.5
Exp/Cntr=0.3,0.1

Type RM Length L Ch R = 1,1346,348,348,348
BEGIN DESCRIPTION:
Stream0186 1.0
END DESCRIPTION:
XS GIS Cut Line= 2
      1816165.14     13944430.48      1816245.87     13943959.15
#Sta/Elev= 30
  4750.3 2025.55  4777.3 2024.63  4791.1 2023.00  4831.9 2019.96  4839.3 2018.59
  4875.6 2015.14  4886.5 2011.80  4891.1 2012.16  4909.4 2011.52  4918.5 2013.21
  4924.6 2013.55  4958.1 2013.20  4982.1 2012.24  4995.7 2010.99  4995.9 2010.49
  4999.4 2010.49  4999.7 2010.99  5021.7 2011.38  5028.1 2012.48  5055.5 2014.82
  5081.3 2018.51  5104.2 2020.46  5110.1 2020.38  5125.5 2022.36  5140.8 2022.88
  5165.1 2024.90  5176.8 2024.90  5183.4 2025.81  5189.5 2025.76  5228.5 2028.62
#Mann=4,-1,0
  4750.3    0.07       0  4831.9     0.1       0  4995.7    0.05       0
  4999.7     0.1       0
Bank Sta=4995.7,4999.7
Exp/Cntr=0.3,0.1

Type RM Length L Ch R = 1,998,337,337,337
BEGIN DESCRIPTION:
Stream0186 0.0
END DESCRIPTION:
XS GIS Cut Line= 3
      1816428.16     13944482.58      1816597.44     13944240.39
      1816383.87     13943847.11
#Sta/Elev= 30
  4611.7 2018.20  4663.6 2016.05  4676.1 2016.42  4717.5 2013.45  4755.7 2012.56
  4786.0 2010.86  4812.5 2010.87  4833.5 2009.90  4881.5 2009.87  4923.9 2007.71
  4934.1 2005.78  4944.3 2005.10  4956.9 2006.75  4978.5 2007.36  4984.2 2006.79
  4992.2 2004.70  5006.5 2004.49  5006.8 2003.99  5010.5 2004.49  5013.0 2005.08
  5024.0 2004.98  5050.6 2007.49  5067.3 2007.02  5086.0 2008.19  5132.5 2008.48
  5139.2 2009.31  5161.2 2009.53  5218.8 2012.78  5306.4 2021.90  5354.7 2029.37
#Mann=4,-1,0
  4611.7    0.07       0  4812.5     0.1       0  5006.5    0.05       0
  5010.5     0.1       0
Bank Sta=5006.5,5010.5
Exp/Cntr=0.3,0.1

Type RM Length L Ch R = 1,661,0,0,0
BEGIN DESCRIPTION:
Stream0186 T
END DESCRIPTION:
XS GIS Cut Line= 3
      1816824.00     13944245.59      1816725.04     13943917.47
      1816331.77     13943690.88
#Sta/Elev= 30
  4541.8 2012.80  4662.8 2012.00  4751.4 2010.71  4769.4 2009.81  4816.4 2009.94
  4923.4 2007.94  4936.6 2006.76  4945.4 2006.89  4965.6 2004.79  4979.5 2001.71
  4996.8 1999.83  5003.7 1999.83  5004.6 1999.06  5005.0 1998.56  5009.7 1999.06
  5033.3 2002.40  5050.9 2003.58  5083.4 2004.15  5094.8 2003.37  5121.2 2003.69
  5128.4 2005.03  5149.8 2012.65  5168.8 2018.33  5244.2 2034.40  5266.2 2036.17
  5277.3 2038.45  5290.4 2038.12  5305.0 2039.92  5315.4 2039.03  5338.4 2039.56
#Mann=3,-1,0
  4541.8     0.1       0  5004.6    0.05       0  5009.7     0.1       0
Bank Sta=5004.6,5009.7
Exp/Cntr=0.3,0.1

Chan Stop Cuts=-1