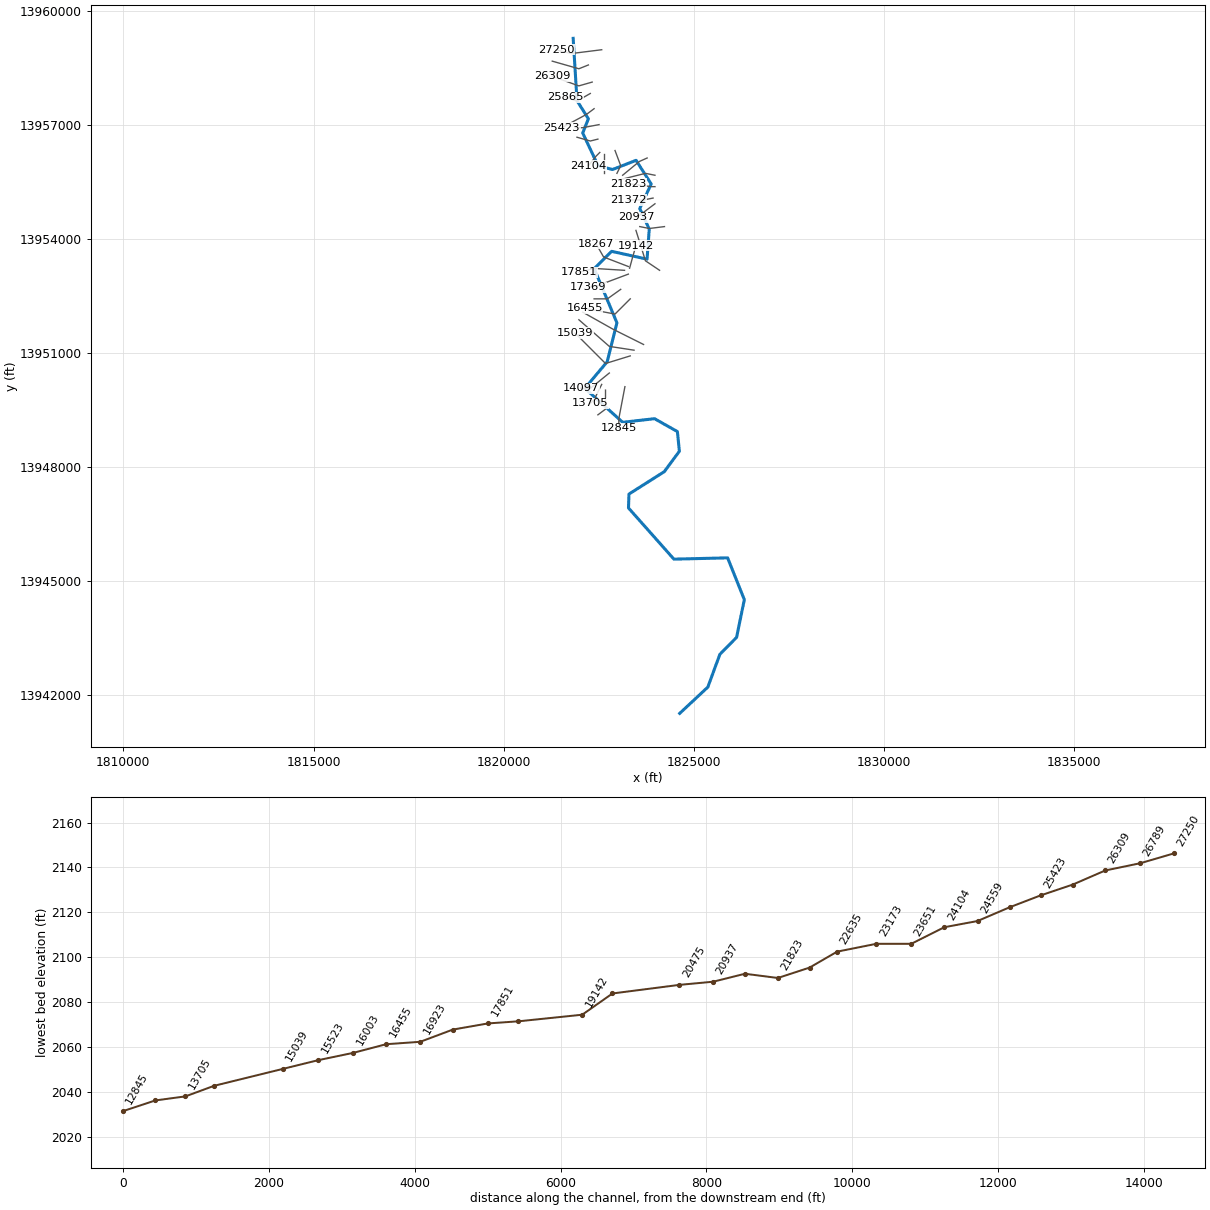
--- Stream0190.prj (project) ---

Proj Title=Stream0190 Base Level Engineering
Current Plan=p01
Default Exp/Contr=0.3,0.1
English Units
Geom File=g01
Flow File=f01
Plan File=p01
BEGIN DESCRIPTION:
Stream0190
END DESCRIPTION:

--- Stream0190.p01 (plan) ---

Plan Title=Multiple Run
Short Identifier=Multiple
Geom File=g01
Flow File=f01
Subcritical Flow
K Sum by GR= 0
Std Step Tol= 0.01
Critical Tol= 0.01
Num of Std Step Trials= 20
Max Error Tol= 0.3
Flow Tol Ratio= 0.001
Split Flow NTrial= 30
Split Flow Tol= 0.02
Split Flow Ratio= 0.02
Log Output Level= 0
Friction Slope Method= 1
Unsteady Friction Slope Method= 2
Unsteady Bridges Friction Slope Method= 1
Parabolic Critical Depth
Global Vel Dist=  1 , 1 , 1
Global Log Level= 0
CheckData=True
Encroach Param= -1, 0, 0, 0
BEGIN DESCRIPTION:
Multiple Run
END DESCRIPTION:

--- Stream0190.f01 (steady flow) ---

Flow Title=Multiple
Number of Profiles=7
Profile Names=10-year,25-year,50-year,1pct_min,100-year,1pct_plu,500-year
River Rch & RM= Stream0190,Reach-1,27250
    1599    2766    3887    2632    5252   10480    9489
River Rch & RM= Stream0190,Reach-1,21823
    2093    3662    5185    3535    7052   14071   12913
River Rch & RM= Stream0190,Reach-1,16923
    2474    4364    6212    4254    8489   16937   15693
River Rch & RM= Stream0190,Reach-1,14097
    2901    5151    7366    5065   10107   20166   18836
River Rch & RM= Stream0190,Reach-1,9218
    3104    5529    7922    5457   10888   21725   20366
River Rch & RM= Stream0190,Reach-1,4489
    3919    7050   10170    7049   14064   28062   26632
Boundary for River Rch & Prof#=Stream0190,Reach-1,1
Up Type=0
Dn Type=3
Dn Slope=0.005
Boundary for River Rch & Prof#=Stream0190,Reach-1,2
Up Type=0
Dn Type=3
Dn Slope=0.005
Boundary for River Rch & Prof#=Stream0190,Reach-1,3
Up Type=0
Dn Type=3
Dn Slope=0.005
Boundary for River Rch & Prof#=Stream0190,Reach-1,4
Up Type=0
Dn Type=3
Dn Slope=0.005
Boundary for River Rch & Prof#=Stream0190,Reach-1,5
Up Type=0
Dn Type=3
Dn Slope=0.005
Boundary for River Rch & Prof#=Stream0190,Reach-1,6
Up Type=0
Dn Type=3
Dn Slope=0.005
Boundary for River Rch & Prof#=Stream0190,Reach-1,7
Up Type=0
Dn Type=3
Dn Slope=0.005

--- Stream0190.g01 (geometry) ---

Geom Title=Existing Conditions

River Reach=Stream0190,Reach-1
Reach XY= 30
      1821825.00     13959275.00      1821925.60     13957635.62
      1822224.64     13957159.73      1822075.99     13956785.30
      1822480.52     13955922.56      1822859.78     13955825.52
      1823478.43     13956067.21      1823875.52     13955445.08
      1823574.80     13954800.08      1823824.63     13954259.73
      1823766.87     13953468.92      1822835.49     13953674.06
      1822377.24     13953219.07      1822974.94     13951795.03
      1822719.48     13950772.56      1822132.61     13950071.67
      1823126.47     13949178.55      1823964.50     13949273.78
      1824564.24     13948934.70      1824617.21     13948418.56
      1824219.38     13947880.62      1823291.43     13947291.77
      1823278.75     13946926.55      1824472.55     13945580.46
      1825884.68     13945614.25      1826323.78     13944514.50
      1826119.48     13943522.56      1825680.83     13943077.30
      1825364.24     13942215.32      1824625.00     13941525.00

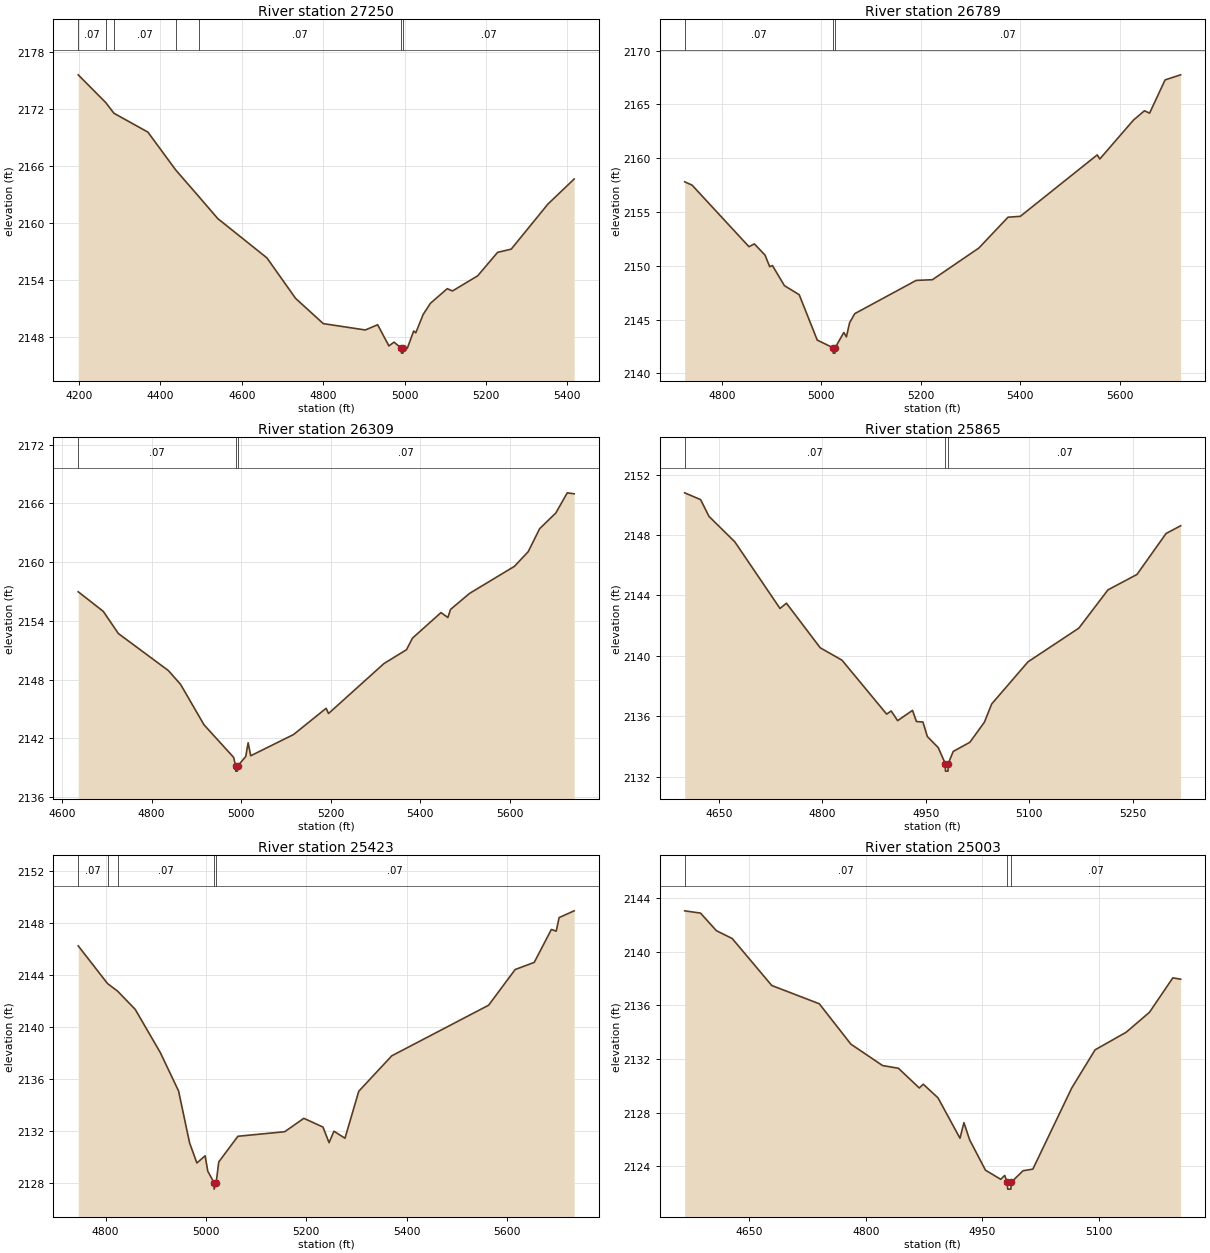
Type RM Length L Ch R = 1,27250,461,461,461
BEGIN DESCRIPTION:
Stream0190 57.0
END DESCRIPTION:
XS GIS Cut Line= 3
      1822575.00     13958975.00      1821775.00     13958875.00
      1821375.03     13958974.99
#Sta/Elev= 30
  4198.1 2175.59  4265.9 2172.66  4285.9 2171.54  4369.4 2169.55  4437.9 2165.55
  4494.1 2162.78  4540.7 2160.45  4661.7 2156.30  4732.2 2152.03  4800.2 2149.37
  4903.5 2148.70  4933.8 2149.25  4961.5 2147.02  4974.1 2147.42  4992.2 2146.76
  4992.4 2146.26  4996.0 2146.26  4996.3 2146.76  5006.9 2146.80  5022.4 2148.59
  5027.5 2148.40  5045.6 2150.33  5063.6 2151.52  5104.8 2153.05  5117.7 2152.81
  5179.6 2154.41  5228.5 2156.88  5262.0 2157.22  5352.2 2161.97  5416.6 2164.61
#Mann=7,-1,0
  4198.1    0.07       0  4265.9     0.1       0  4285.9    0.07       0
  4437.9     0.1       0  4494.1    0.07       0  4992.2    0.05       0
  4996.3    0.07       0
Bank Sta=4992.2,4996.3
Exp/Cntr=0.3,0.1

Type RM Length L Ch R = 1,26789,480,480,480
BEGIN DESCRIPTION:
Stream0190 56.0
END DESCRIPTION:
XS GIS Cut Line= 3
      1822225.04     13958575.02      1821975.00     13958475.00
      1821275.01     13958675.00
#Sta/Elev= 30
  4725.2 2157.80  4740.1 2157.49  4854.5 2151.77  4865.3 2152.03  4886.8 2150.99
  4896.2 2149.91  4901.6 2150.02  4925.8 2148.15  4955.5 2147.31  4991.8 2143.09
  5023.6 2142.38  5023.9 2141.88  5027.5 2141.88  5027.8 2142.38  5045.2 2143.80
  5050.4 2143.39  5056.9 2144.71  5067.3 2145.55  5190.8 2148.64  5223.3 2148.70
  5316.9 2151.65  5375.4 2154.51  5400.1 2154.59  5554.8 2160.30  5560.0 2159.92
  5627.6 2163.53  5649.7 2164.40  5660.1 2164.18  5691.3 2167.27  5722.5 2167.74
#Mann=3,-1,0
  4725.2    0.07       0  5023.6    0.05       0  5027.8    0.07       0
Bank Sta=5023.6,5027.8
Exp/Cntr=0.3,0.1

Type RM Length L Ch R = 1,26309,444,444,444
BEGIN DESCRIPTION:
Stream0190 55.0
END DESCRIPTION:
XS GIS Cut Line= 3
      1822324.99     13958125.00      1821975.00     13958025.00
      1821275.00     13958275.00
#Sta/Elev= 30
  4636.1 2156.98  4692.0 2154.98  4725.8 2152.71  4837.6 2148.92  4864.9 2147.50
  4916.9 2143.39  4983.2 2140.05  4987.6 2139.15  4987.8 2138.65  4991.5 2138.65
  4991.8 2139.15  5010.2 2140.15  5015.5 2141.55  5021.3 2140.22  5116.9 2142.39
  5189.6 2145.07  5195.0 2144.54  5318.7 2149.64  5369.1 2151.06  5382.4 2152.24
  5446.1 2154.85  5461.5 2154.35  5467.3 2155.17  5509.8 2156.81  5610.1 2159.58
  5640.9 2161.08  5666.4 2163.43  5702.5 2165.03  5728.0 2167.09  5743.4 2166.99
#Mann=3,-1,0
  4636.1    0.07       0  4987.6    0.05       0  4991.8    0.07       0
Bank Sta=4987.6,4991.8
Exp/Cntr=0.3,0.1

Type RM Length L Ch R = 1,25865,442,442,442
BEGIN DESCRIPTION:
Stream0190 54.0
END DESCRIPTION:
XS GIS Cut Line= 3
      1822275.04     13957825.02      1821925.00     13957625.00
      1821624.98     13957725.01
#Sta/Elev= 30
  4600.4 2150.79  4623.5 2150.34  4635.7 2149.23  4673.1 2147.55  4738.7 2143.14
  4748.0 2143.49  4797.0 2140.54  4828.6 2139.72  4893.4 2136.15  4899.9 2136.36
  4909.3 2135.72  4930.9 2136.40  4936.6 2135.66  4946.0 2135.63  4952.4 2134.67
  4968.3 2133.93  4978.4 2132.88  4978.7 2132.38  4982.4 2132.38  4982.7 2132.88
  4989.9 2133.68  5014.1 2134.29  5035.2 2135.62  5045.7 2136.82  5098.4 2139.61
  5172.2 2141.84  5214.4 2144.37  5256.5 2145.39  5298.7 2148.10  5319.8 2148.61
#Mann=3,-1,0
  4600.4    0.07       0  4978.4    0.05       0  4982.7    0.07       0
Bank Sta=4978.4,4982.7
Exp/Cntr=0.3,0.1

Type RM Length L Ch R = 1,25423,420,420,420
BEGIN DESCRIPTION:
Stream0190 53.0
END DESCRIPTION:
XS GIS Cut Line= 3
      1822375.04     13957425.03      1822175.00     13957275.00
      1821524.99     13956924.99
#Sta/Elev= 30
  4745.4 2146.23  4803.9 2143.33  4823.9 2142.75  4859.0 2141.35  4909.0 2138.03
  4945.4 2135.08  4967.3 2131.10  4981.9 2129.55  4998.3 2130.10  5003.6 2128.92
  5016.0 2128.04  5016.3 2127.54  5020.3 2128.04  5025.5 2129.63  5063.6 2131.60
  5156.9 2131.95  5195.0 2132.98  5233.1 2132.31  5245.3 2131.11  5255.0 2131.99
  5277.0 2131.45  5304.5 2135.06  5370.2 2137.78  5563.3 2141.67  5616.1 2144.41
  5654.2 2144.96  5688.3 2147.49  5698.0 2147.36  5703.7 2148.40  5733.7 2148.92
#Mann=5,-1,0
  4745.4    0.07       0  4803.9     0.1       0  4823.9    0.07       0
  5016.0    0.05       0  5020.3    0.07       0
Bank Sta=5016,5020.3
Exp/Cntr=0.3,0.1

Type RM Length L Ch R = 1,25003,444,444,444
BEGIN DESCRIPTION:
Stream0190 52.0
END DESCRIPTION:
XS GIS Cut Line= 3
      1822505.05     13957006.31      1822075.00     13956925.00
      1821874.97     13956925.00
#Sta/Elev= 30
  4567.1 2143.03  4587.5 2142.86  4607.9 2141.55  4628.2 2140.97  4679.1 2137.47
  4740.2 2136.11  4780.9 2133.10  4821.6 2131.51  4841.9 2131.31  4868.8 2129.84
  4873.9 2130.12  4892.8 2129.11  4921.1 2126.10  4926.2 2127.26  4933.5 2125.98
  4953.9 2123.72  4973.5 2123.04  4978.6 2123.33  4982.0 2122.81  4982.4 2122.31
  4986.5 2122.31  4986.8 2122.81  5002.2 2123.68  5014.8 2123.80  5064.8 2129.84
  5094.8 2132.68  5134.8 2133.99  5164.8 2135.48  5194.8 2138.04  5204.8 2137.94
#Mann=3,-1,0
  4567.1    0.07       0  4982.0    0.05       0  4986.8    0.07       0
Bank Sta=4982,4986.8
Exp/Cntr=0.3,0.1

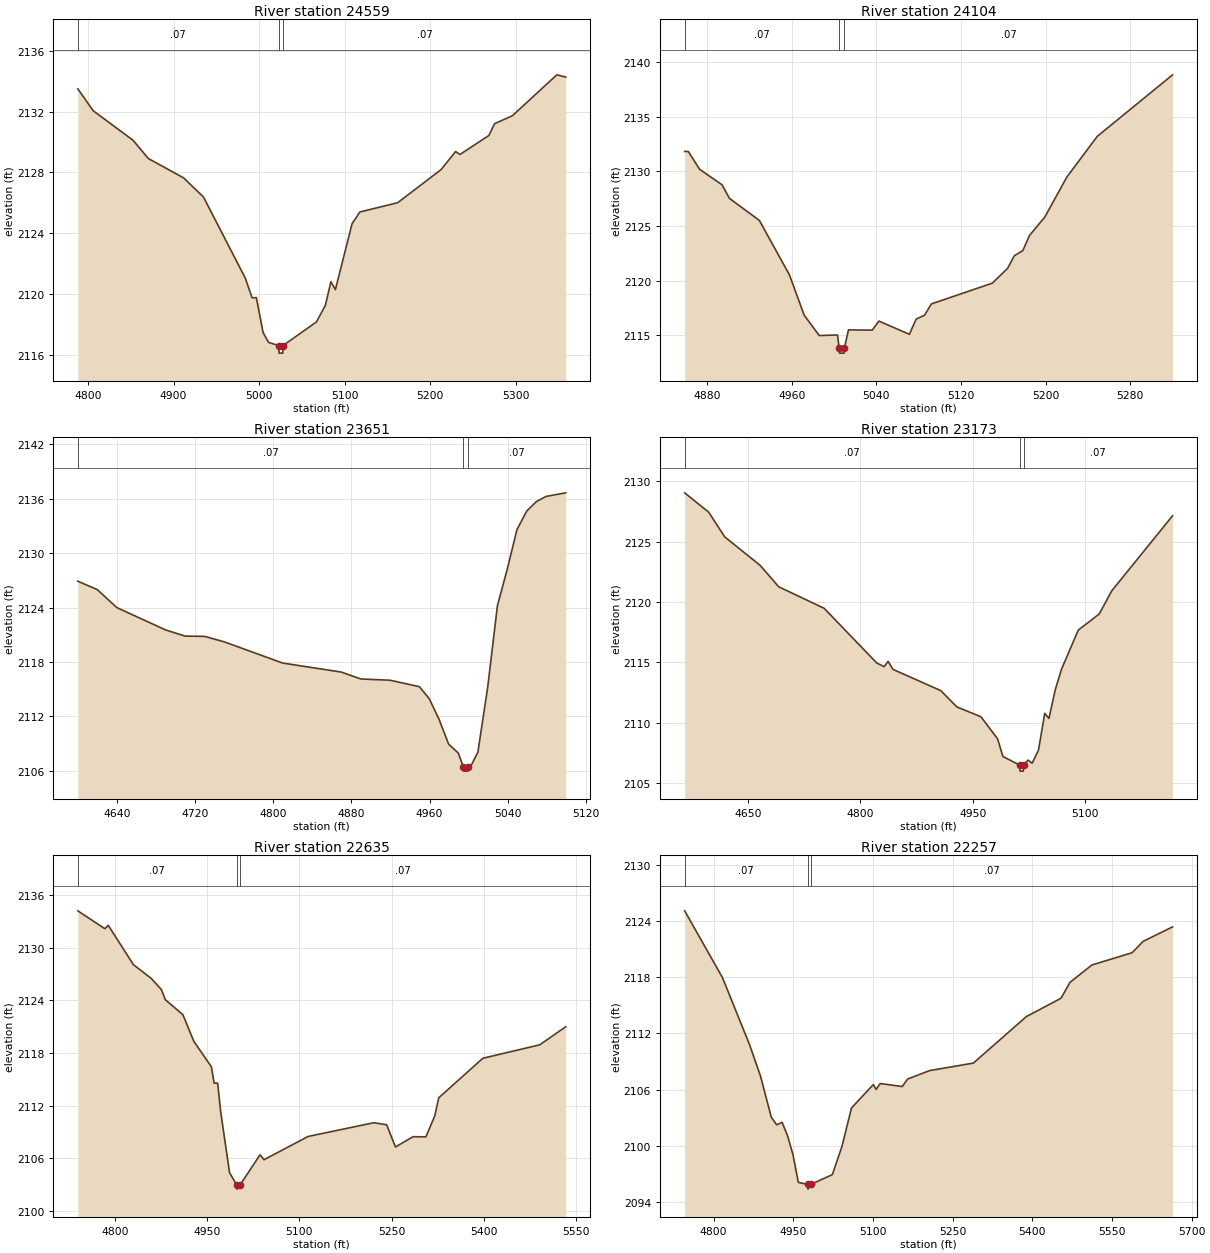
Type RM Length L Ch R = 1,24559,455,455,455
BEGIN DESCRIPTION:
Stream0190 51.0
END DESCRIPTION:
XS GIS Cut Line= 3
      1822474.99     13956625.00      1822275.00     13956575.00
      1821924.95     13956675.01
#Sta/Elev= 30
  4788.1 2133.49  4806.1 2132.05  4852.5 2130.12  4870.6 2128.91  4911.8 2127.64
  4935.0 2126.38  4983.9 2121.05  4991.7 2119.77  4996.8 2119.77  5004.6 2117.48
  5011.1 2116.83  5022.9 2116.63  5023.3 2116.13  5027.6 2116.13  5028.0 2116.63
  5067.0 2118.18  5077.4 2119.27  5083.9 2120.82  5089.1 2120.30  5108.6 2124.63
  5117.7 2125.40  5161.9 2126.01  5212.7 2128.19  5229.6 2129.37  5234.8 2129.18
  5268.6 2130.43  5275.1 2131.20  5295.9 2131.72  5347.9 2134.41  5358.3 2134.26
#Mann=3,-1,0
  4788.1    0.07       0  5022.9    0.05       0  5028.0    0.07       0
Bank Sta=5022.9,5028
Exp/Cntr=0.3,0.1

Type RM Length L Ch R = 1,24104,453,453,453
BEGIN DESCRIPTION:
Stream0190 50.0
END DESCRIPTION:
XS GIS Cut Line= 3
      1822524.98     13956274.98      1822425.00     13956175.00
      1822224.97     13955924.97
#Sta/Elev= 30
  4858.6 2131.81  4862.1 2131.81  4872.7 2130.18  4893.9 2128.77  4901.0 2127.52
  4929.3 2125.50  4957.6 2120.55  4971.7 2116.84  4985.9 2114.98  5003.2 2115.03
  5004.7 2113.87  5005.1 2113.37  5009.4 2113.37  5009.8 2113.87  5013.6 2115.50
  5036.0 2115.47  5042.4 2116.30  5071.2 2115.09  5077.6 2116.48  5085.6 2116.84
  5092.0 2117.87  5149.7 2119.77  5164.1 2121.12  5170.5 2122.28  5178.5 2122.74
  5184.9 2124.14  5199.3 2125.81  5220.1 2129.46  5248.9 2133.19  5320.2 2138.82
#Mann=3,-1,0
  4858.6    0.07       0  5004.7    0.05       0  5009.8    0.07       0
Bank Sta=5004.7,5009.8
Exp/Cntr=0.3,0.1

Type RM Length L Ch R = 1,23651,478,478,478
BEGIN DESCRIPTION:
Stream0190 49.0
END DESCRIPTION:
XS GIS Cut Line= 3
      1822625.00     13956224.96      1822625.00     13955825.00
      1822625.00     13955724.96
#Sta/Elev= 30
  4599.6 2126.90  4619.6 2125.97  4639.6 2123.99  4689.6 2121.53  4709.6 2120.85
  4729.6 2120.82  4749.6 2120.22  4809.6 2117.88  4869.6 2116.89  4889.6 2116.13
  4919.6 2115.99  4949.6 2115.28  4959.6 2113.98  4969.6 2111.74  4979.6 2108.95
  4989.6 2107.96  4994.5 2106.48  4994.9 2105.98  4999.3 2105.98  4999.6 2106.48
  5002.1 2106.48  5009.6 2108.07  5019.6 2115.19  5029.6 2124.20  5039.6 2128.19
  5049.6 2132.57  5059.6 2134.62  5069.6 2135.67  5079.6 2136.24  5099.6 2136.63
#Mann=3,-1,0
  4599.6    0.07       0  4994.5    0.05       0  4999.6    0.07       0
Bank Sta=4994.5,4999.6
Exp/Cntr=0.3,0.1

Type RM Length L Ch R = 1,23173,538,538,538
BEGIN DESCRIPTION:
Stream0190 48.0
END DESCRIPTION:
XS GIS Cut Line= 3
      1822925.01     13956324.98      1823075.00     13955925.00
      1822974.99     13955724.99
#Sta/Elev= 30
  4565.7 2129.06  4597.7 2127.46  4619.1 2125.41  4666.3 2123.05  4691.2 2121.27
  4751.7 2119.49  4822.0 2114.95  4831.8 2114.65  4837.1 2115.09  4843.4 2114.43
  4907.4 2112.66  4928.8 2111.31  4960.8 2110.50  4983.1 2108.67  4990.2 2107.20
  5012.6 2106.49  5013.0 2105.99  5017.4 2105.99  5017.8 2106.49  5023.6 2106.90
  5029.2 2106.65  5037.6 2107.72  5046.0 2110.78  5051.6 2110.36  5060.0 2112.74
  5068.3 2114.43  5090.7 2117.68  5118.7 2119.02  5135.4 2120.94  5216.5 2127.16
#Mann=3,-1,0
  4565.7    0.07       0  5012.6    0.05       0  5017.8    0.07       0
Bank Sta=5012.6,5017.8
Exp/Cntr=0.3,0.1

Type RM Length L Ch R = 1,22635,378,378,378
BEGIN DESCRIPTION:
Stream0190 47.0
END DESCRIPTION:
XS GIS Cut Line= 3
      1823768.98     13956128.52      1823563.56     13956036.42
      1823125.01     13955675.01
#Sta/Elev= 30
  4739.9 2134.18  4783.9 2132.14  4789.4 2132.53  4830.3 2128.05  4858.9 2126.51
  4875.8 2125.22  4882.1 2124.07  4910.8 2122.35  4928.5 2119.33  4957.1 2116.42
  4961.5 2114.56  4967.3 2114.56  4972.4 2111.21  4986.7 2104.35  4998.2 2102.99
  4998.7 2102.49  5004.0 2102.99  5036.2 2106.40  5042.7 2105.84  5114.4 2108.49
  5221.3 2110.05  5242.1 2109.82  5256.4 2107.29  5285.1 2108.46  5305.9 2108.44
  5320.3 2110.82  5326.8 2112.89  5398.5 2117.39  5491.0 2118.92  5533.3 2120.98
#Mann=3,-1,0
  4739.9    0.07       0  4998.2    0.05       0  5004.0    0.07       0
Bank Sta=4998.2,5004
Exp/Cntr=0.3,0.1

Type RM Length L Ch R = 1,22257,434,434,434
BEGIN DESCRIPTION:
Stream0190 46.0
END DESCRIPTION:
XS GIS Cut Line= 3
      1823974.96     13955675.01      1823725.00     13955725.00
      1823081.20     13955563.36
#Sta/Elev= 30
  4745.4 2125.07  4816.7 2117.93  4867.7 2110.77  4888.1 2107.45  4908.5 2103.05
  4918.7 2102.23  4928.9 2102.50  4939.1 2101.07  4949.3 2099.06  4959.5 2096.09
  4977.0 2095.87  4977.5 2095.37  4982.8 2095.87  5023.5 2096.92  5041.6 2099.93
  5059.5 2104.03  5100.6 2106.53  5105.8 2106.01  5113.7 2106.64  5155.0 2106.32
  5165.3 2107.12  5206.5 2108.02  5289.0 2108.82  5388.7 2113.78  5454.0 2115.74
  5471.0 2117.44  5512.2 2119.29  5588.0 2120.60  5608.6 2121.81  5664.1 2123.36
#Mann=3,-1,0
  4745.4    0.07       0  4977.0    0.05       0  4982.8    0.07       0
Bank Sta=4977,4982.8
Exp/Cntr=0.3,0.1

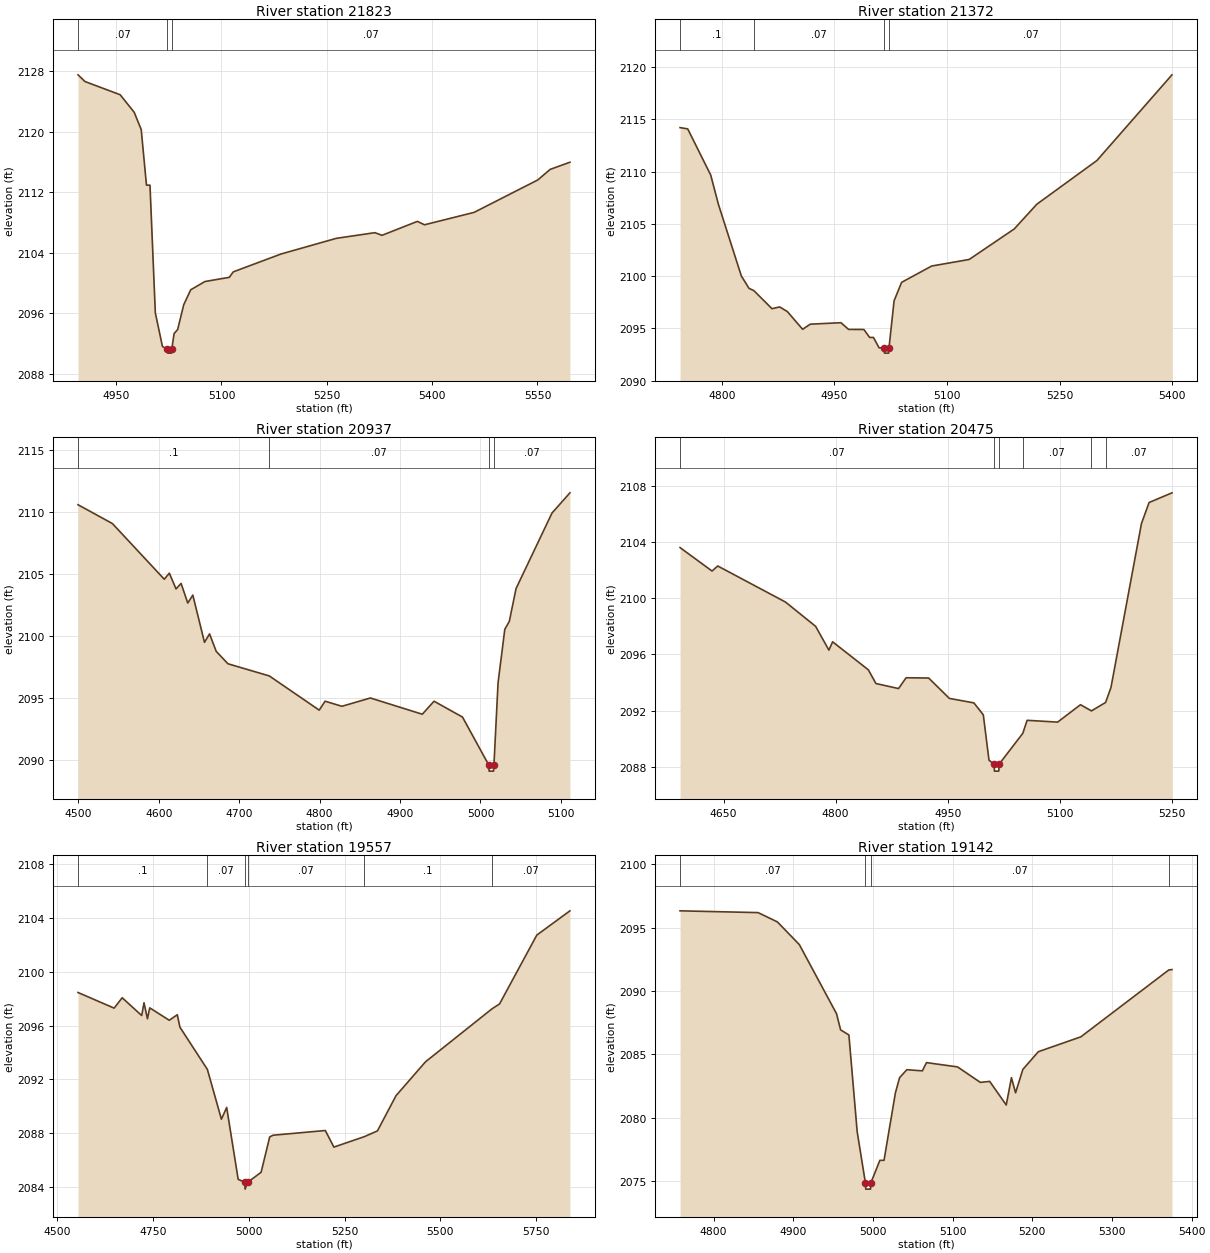
Type RM Length L Ch R = 1,21823,451,451,451
BEGIN DESCRIPTION:
Stream0190 45.0
END DESCRIPTION:
XS GIS Cut Line= 3
      1823975.03     13955375.00      1823875.00     13955375.00
      1823279.66     13955453.37
#Sta/Elev= 30
  4895.7 2127.54  4905.7 2126.65  4955.7 2124.91  4975.7 2122.59  4985.7 2120.31
  4993.2 2112.96  4998.2 2112.96  5005.8 2096.09  5015.9 2091.65  5022.8 2091.26
  5023.3 2090.76  5028.7 2090.76  5029.2 2091.26  5032.5 2093.34  5037.6 2093.88
  5046.2 2097.14  5056.2 2099.13  5076.4 2100.22  5111.2 2100.78  5116.8 2101.50
  5184.8 2103.86  5263.5 2105.93  5318.5 2106.68  5328.6 2106.33  5379.0 2108.17
  5389.1 2107.72  5459.7 2109.36  5550.5 2113.65  5568.0 2115.04  5596.2 2115.99
#Mann=3,-1,0
  4895.7    0.07       0  5022.8    0.05       0  5029.2    0.07       0
Bank Sta=5022.8,5029.2
Exp/Cntr=0.3,0.1

Type RM Length L Ch R = 1,21372,435,435,435
BEGIN DESCRIPTION:
Stream0190 44.0
END DESCRIPTION:
XS GIS Cut Line= 3
      1823925.00     13955075.00      1823675.00     13955025.00
      1823274.95     13955025.00
#Sta/Elev= 30
  4744.4 2114.21  4754.6 2114.09  4785.2 2109.68  4795.4 2106.89  4826.0 2100.02
  4836.2 2098.84  4842.8 2098.61  4866.8 2096.89  4877.0 2097.06  4887.2 2096.62
  4907.6 2094.92  4917.8 2095.41  4958.6 2095.55  4968.8 2094.91  4989.2 2094.90
  4996.8 2094.14  5001.9 2094.14  5009.4 2093.15  5016.1 2093.14  5016.6 2092.64
  5022.1 2092.64  5022.6 2093.14  5029.4 2097.65  5039.4 2099.41  5079.4 2100.97
  5129.4 2101.60  5189.4 2104.52  5219.4 2106.88  5299.4 2111.06  5399.4 2119.26
#Mann=4,-1,0
  4744.4     0.1       0  4842.8    0.07       0  5016.1    0.05       0
  5022.6    0.07       0
Bank Sta=5016.1,5022.6
Exp/Cntr=0.3,0.1

Type RM Length L Ch R = 1,20937,462,462,462
BEGIN DESCRIPTION:
Stream0190 43.0
END DESCRIPTION:
XS GIS Cut Line= 3
      1823975.04     13954925.03      1823575.00     13954625.00
      1823475.04     13954575.02
#Sta/Elev= 30
  4499.5 2110.59  4542.3 2109.07  4606.8 2104.58  4613.1 2105.07  4621.4 2103.80
  4627.7 2104.24  4636.0 2102.66  4642.3 2103.30  4656.8 2099.49  4663.1 2100.17
  4671.4 2098.76  4686.0 2097.76  4737.4 2096.78  4799.5 2094.02  4806.8 2094.74
  4827.7 2094.33  4863.1 2095.00  4927.7 2093.69  4942.3 2094.74  4977.7 2093.46
  5010.3 2089.60  5010.8 2089.10  5016.3 2089.10  5016.8 2089.60  5021.9 2096.22
  5030.3 2100.54  5035.9 2101.18  5044.3 2103.83  5089.0 2109.92  5111.3 2111.55
#Mann=4,-1,0
  4499.5     0.1       0  4737.4    0.07       0  5010.3    0.05       0
  5016.8    0.07       0
Bank Sta=5010.3,5016.8
Exp/Cntr=0.3,0.1

Type RM Length L Ch R = 1,20475,918,918,918
BEGIN DESCRIPTION:
Stream0190 42.0
END DESCRIPTION:
XS GIS Cut Line= 3
      1824225.02     13954325.00      1823825.00     13954275.00
      1823574.98     13954325.00
#Sta/Elev= 30
  4591.8 2103.61  4634.6 2101.94  4642.2 2102.30  4732.9 2099.73  4773.2 2098.00
  4790.9 2096.31  4795.9 2096.90  4843.8 2094.90  4853.8 2093.93  4884.1 2093.57
  4894.2 2094.34  4924.4 2094.32  4952.1 2092.87  4984.9 2092.55  4997.5 2091.70
  5005.1 2088.47  5011.9 2088.19  5012.4 2087.69  5018.2 2087.69  5018.7 2088.19
  5050.3 2090.38  5056.1 2091.31  5096.9 2091.18  5127.5 2092.42  5142.2 2091.98
  5161.1 2092.58  5168.3 2093.65  5209.1 2105.33  5219.3 2106.82  5249.9 2107.51
#Mann=6,-1,0
  4591.8    0.07       0  5011.9    0.05       0  5018.7    0.07       0
  5050.3    0.07       0  5142.2     0.1       0  5161.1    0.07       0
Bank Sta=5011.9,5018.7
Exp/Cntr=0.3,0.1

Type RM Length L Ch R = 1,19557,415,415,415
BEGIN DESCRIPTION:
Stream0190 41.0
END DESCRIPTION:
XS GIS Cut Line= 3
      1824095.88     13953175.65      1823725.00     13953425.00
      1823474.99     13954225.04
#Sta/Elev= 30
  4553.6 2098.45  4648.0 2097.29  4669.0 2098.06  4720.0 2096.74  4726.0 2097.69
  4735.0 2096.50  4741.0 2097.31  4792.0 2096.39  4813.0 2096.80  4819.8 2095.88
  4891.6 2092.74  4928.2 2089.05  4942.0 2089.92  4972.0 2084.59  4989.6 2084.36
  4990.1 2083.86  4996.5 2084.36  5031.9 2085.11  5054.5 2087.74  5063.4 2087.86
  5199.6 2088.21  5222.1 2086.98  5301.3 2087.75  5335.8 2088.18  5384.5 2090.80
  5461.5 2093.31  5635.2 2097.24  5654.8 2097.60  5752.2 2102.71  5838.7 2104.51
#Mann=6,-1,0
  4553.6     0.1       0  4891.6    0.07       0  4989.6    0.05       0
  4996.5    0.07       0  5301.3     0.1       0  5635.2    0.07       0
Bank Sta=4989.6,4996.5
Exp/Cntr=0.3,0.1

Type RM Length L Ch R = 1,19142,875,875,875
BEGIN DESCRIPTION:
Stream0190 40.0
END DESCRIPTION:
XS GIS Cut Line= 3
      1823308.35     13953230.55      1823375.00     13953475.00
      1823475.01     13953825.02
#Sta/Elev= 30
  4757.9 2096.32  4855.8 2096.18  4880.0 2095.45  4907.6 2093.66  4954.3 2088.21
  4959.4 2086.94  4969.8 2086.54  4980.2 2078.92  4990.5 2074.89  4991.0 2074.39
  4996.9 2074.39  4997.4 2074.89  5008.7 2076.66  5013.9 2076.66  5028.2 2081.98
  5033.4 2083.17  5042.5 2083.80  5062.0 2083.71  5067.2 2084.36  5106.2 2084.02
  5134.8 2082.80  5146.5 2082.88  5167.3 2081.02  5173.8 2083.17  5179.0 2081.98
  5188.1 2083.82  5207.6 2085.22  5260.9 2086.39  5371.3 2091.66  5375.3 2091.69
#Mann=4,-1,0
  4757.9    0.07       0  4990.5    0.05       0  4997.4    0.07       0
  5371.3     0.1       0
Bank Sta=4990.5,4997.4
Exp/Cntr=0.3,0.1

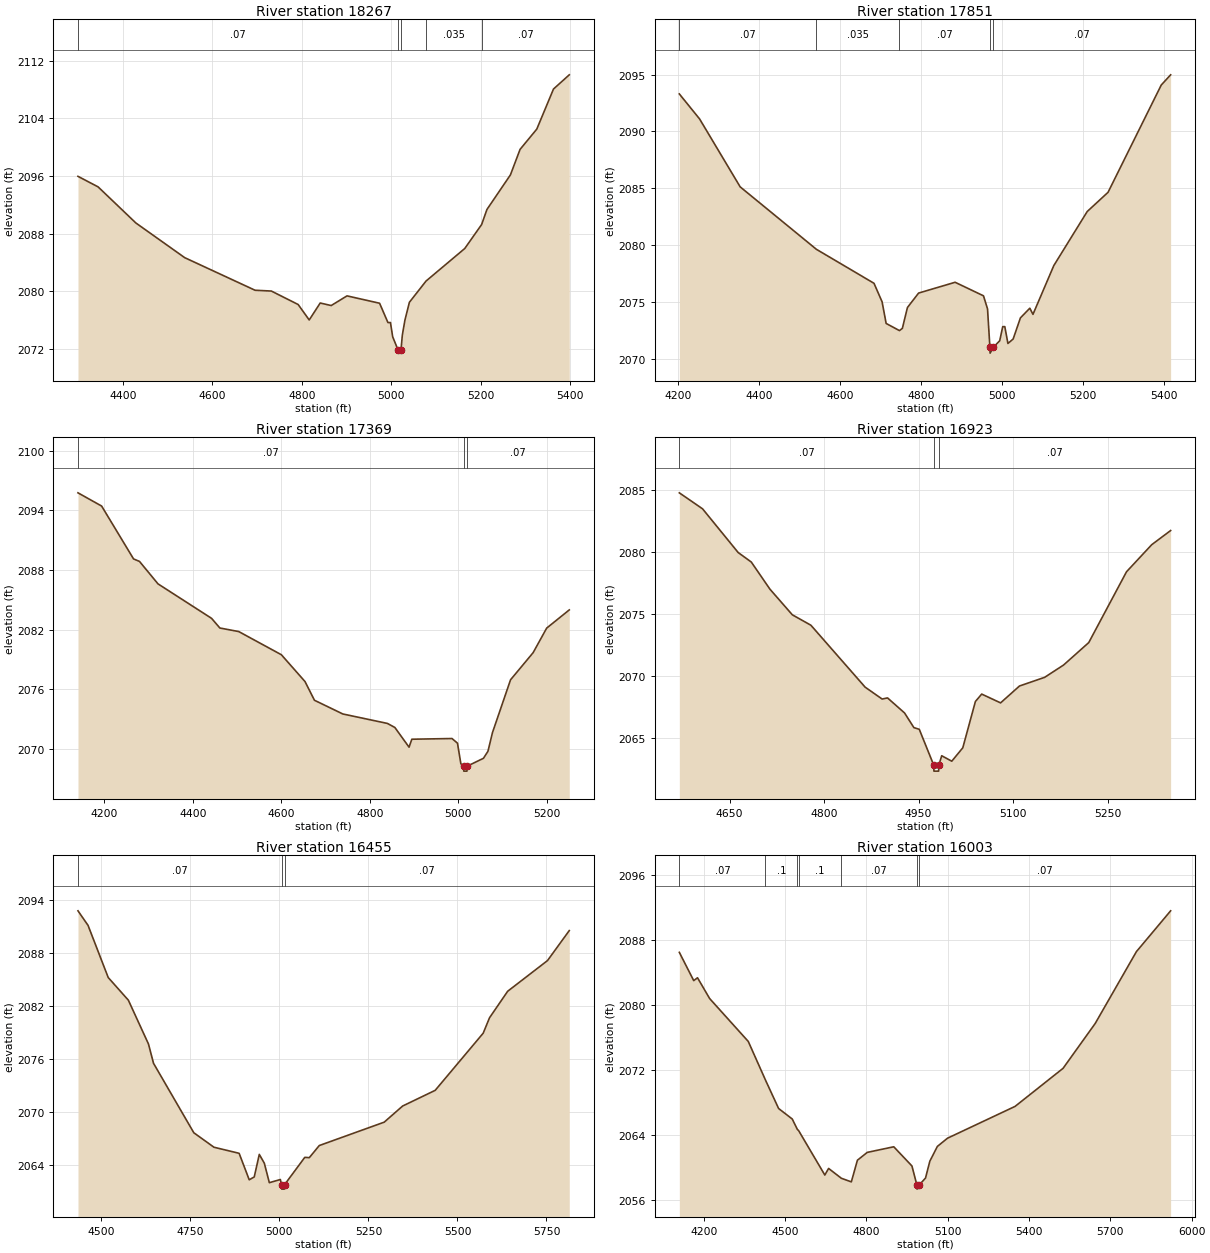
Type RM Length L Ch R = 1,18267,416,416,416
BEGIN DESCRIPTION:
Stream0190 39.0
END DESCRIPTION:
XS GIS Cut Line= 3
      1823274.97     13953275.01      1822625.00     13953525.00
      1822425.00     13953875.00
#Sta/Elev= 30
  4299.0 2095.97  4344.0 2094.51  4428.6 2089.50  4537.9 2084.69  4695.4 2080.17
  4731.8 2080.06  4791.8 2078.19  4816.5 2076.05  4841.1 2078.40  4865.7 2078.05
  4901.1 2079.39  4974.0 2078.37  4992.7 2075.69  4998.3 2075.69  5003.3 2073.72
  5014.9 2071.95  5015.4 2071.45  5022.0 2071.95  5024.9 2073.95  5030.7 2076.03
  5040.7 2078.50  5078.0 2081.45  5164.6 2085.96  5202.4 2089.29  5214.2 2091.37
  5266.8 2096.17  5288.4 2099.71  5325.8 2102.52  5363.2 2108.08  5398.5 2110.05
#Mann=5,-1,0
  4299.0    0.07       0  5014.9    0.05       0  5022.0    0.07       0
  5078.0   0.035       0  5202.4    0.07       0
Bank Sta=5014.9,5022
Exp/Cntr=0.3,0.1

Type RM Length L Ch R = 1,17851,482,482,482
BEGIN DESCRIPTION:
Stream0190 38.0
END DESCRIPTION:
XS GIS Cut Line= 3
      1823175.04     13953175.00      1822375.00     13953225.00
      1821975.01     13953125.00
#Sta/Elev= 30
  4202.8 2093.30  4252.9 2091.10  4353.1 2085.13  4541.4 2079.64  4683.8 2076.65
  4703.8 2075.02  4713.8 2073.12  4746.7 2072.49  4753.9 2072.69  4766.4 2074.52
  4794.0 2075.79  4884.2 2076.74  4954.3 2075.55  4964.3 2074.40  4970.2 2071.01
  4970.7 2070.51  4978.4 2071.01  4994.4 2071.60  5001.9 2072.84  5007.0 2072.84
  5014.7 2071.36  5027.6 2071.75  5045.6 2073.61  5068.8 2074.46  5076.6 2073.92
  5128.1 2078.21  5210.6 2082.96  5262.1 2084.65  5393.5 2094.08  5416.7 2094.98
#Mann=5,-1,0
  4202.8    0.07       0  4541.4   0.035       0  4746.7    0.07       0
  4970.2    0.05       0  4978.4    0.07       0
Bank Sta=4970.2,4978.4
Exp/Cntr=0.3,0.1

Type RM Length L Ch R = 1,17369,446,446,446
BEGIN DESCRIPTION:
Stream0190 37.0
END DESCRIPTION:
XS GIS Cut Line= 3
      1823275.02     13953075.01      1822475.00     13952775.00
      1822224.97     13952724.99
#Sta/Elev= 30
  4140.9 2095.77  4194.3 2094.44  4266.4 2089.12  4279.8 2088.87  4321.6 2086.61
  4442.6 2083.14  4461.3 2082.17  4504.0 2081.81  4600.2 2079.48  4653.6 2076.78
  4674.9 2074.90  4739.0 2073.52  4839.6 2072.57  4856.5 2072.16  4888.5 2070.18
  4894.8 2070.98  4985.5 2071.05  4997.9 2070.58  5005.5 2068.51  5011.6 2068.27
  5012.1 2067.77  5019.3 2067.77  5019.8 2068.27  5056.5 2069.06  5066.7 2069.77
  5076.9 2071.65  5117.7 2076.96  5168.7 2079.69  5199.3 2082.16  5250.3 2083.99
#Mann=3,-1,0
  4140.9    0.07       0  5011.6    0.05       0  5019.8    0.07       0
Bank Sta=5011.6,5019.8
Exp/Cntr=0.3,0.1

Type RM Length L Ch R = 1,16923,468,468,468
BEGIN DESCRIPTION:
Stream0190 36.0
END DESCRIPTION:
XS GIS Cut Line= 3
      1823075.02     13952675.01      1822725.00     13952425.00
      1822375.04     13952425.00
#Sta/Elev= 30
  4570.1 2084.76  4607.0 2083.47  4663.5 2079.95  4684.4 2079.18  4713.9 2077.00
  4749.5 2074.93  4779.0 2074.09  4865.1 2069.10  4892.1 2068.14  4900.7 2068.23
  4927.7 2067.02  4942.5 2065.84  4951.1 2065.70  4973.9 2062.83  4974.4 2062.33
  4981.8 2062.33  4982.3 2062.83  4986.7 2063.57  5002.7 2063.13  5020.2 2064.21
  5040.2 2067.94  5050.2 2068.54  5080.2 2067.83  5110.2 2069.19  5150.2 2069.89
  5180.2 2070.88  5220.2 2072.69  5280.2 2078.40  5320.2 2080.58  5350.2 2081.72
#Mann=3,-1,0
  4570.1    0.07       0  4973.9    0.05       0  4982.3    0.07       0
Bank Sta=4973.9,4982.3
Exp/Cntr=0.3,0.1

Type RM Length L Ch R = 1,16455,452,452,452
BEGIN DESCRIPTION:
Stream0190 35.0
END DESCRIPTION:
XS GIS Cut Line= 3
      1823325.03     13952425.03      1822925.00     13952025.00
      1822124.97     13952175.01
#Sta/Elev= 30
  4434.3 2092.80  4462.6 2091.15  4519.2 2085.24  4575.8 2082.67  4632.3 2077.70
  4646.5 2075.51  4759.6 2067.64  4816.2 2066.00  4886.9 2065.31  4915.2 2062.31
  4929.3 2062.63  4943.5 2065.19  4957.6 2064.19  4971.7 2061.98  5002.6 2062.34
  5006.0 2061.75  5006.5 2061.25  5013.9 2061.25  5014.4 2061.75  5071.2 2064.85
  5084.0 2064.82  5111.9 2066.19  5294.2 2068.84  5346.0 2070.67  5437.5 2072.45
  5572.3 2078.93  5590.1 2080.68  5641.0 2083.68  5752.9 2087.16  5814.0 2090.56
#Mann=3,-1,0
  4434.3    0.07       0  5006.0    0.05       0  5014.4    0.07       0
Bank Sta=5006,5014.4
Exp/Cntr=0.3,0.1

Type RM Length L Ch R = 1,16003,480,480,480
BEGIN DESCRIPTION:
Stream0190 34.0
END DESCRIPTION:
XS GIS Cut Line= 3
      1823675.01     13951225.00      1822875.00     13951625.00
      1822075.01     13952074.99
#Sta/Elev= 30
  4110.1 2086.46  4163.2 2082.99  4177.2 2083.34  4221.9 2080.79  4364.5 2075.52
  4427.9 2070.78  4476.3 2067.29  4526.6 2066.00  4545.4 2064.73  4549.9 2064.59
  4646.8 2059.12  4660.7 2059.93  4708.0 2058.72  4744.6 2058.28  4767.0 2060.94
  4803.3 2061.90  4901.1 2062.59  4968.2 2060.23  4986.4 2057.89  4986.9 2057.39
  4994.8 2057.89  5018.2 2058.75  5034.2 2060.82  5061.9 2062.63  5099.2 2063.64
  5348.7 2067.55  5525.6 2072.22  5644.2 2077.73  5796.2 2086.55  5922.4 2091.56
#Mann=7,-1,0
  4110.1    0.07       0  4427.9     0.1       0  4545.4    0.07       0
  4549.9     0.1       0  4708.0    0.07       0  4986.4    0.05       0
  4994.8    0.07       0
Bank Sta=4986.4,4994.8
Exp/Cntr=0.3,0.1

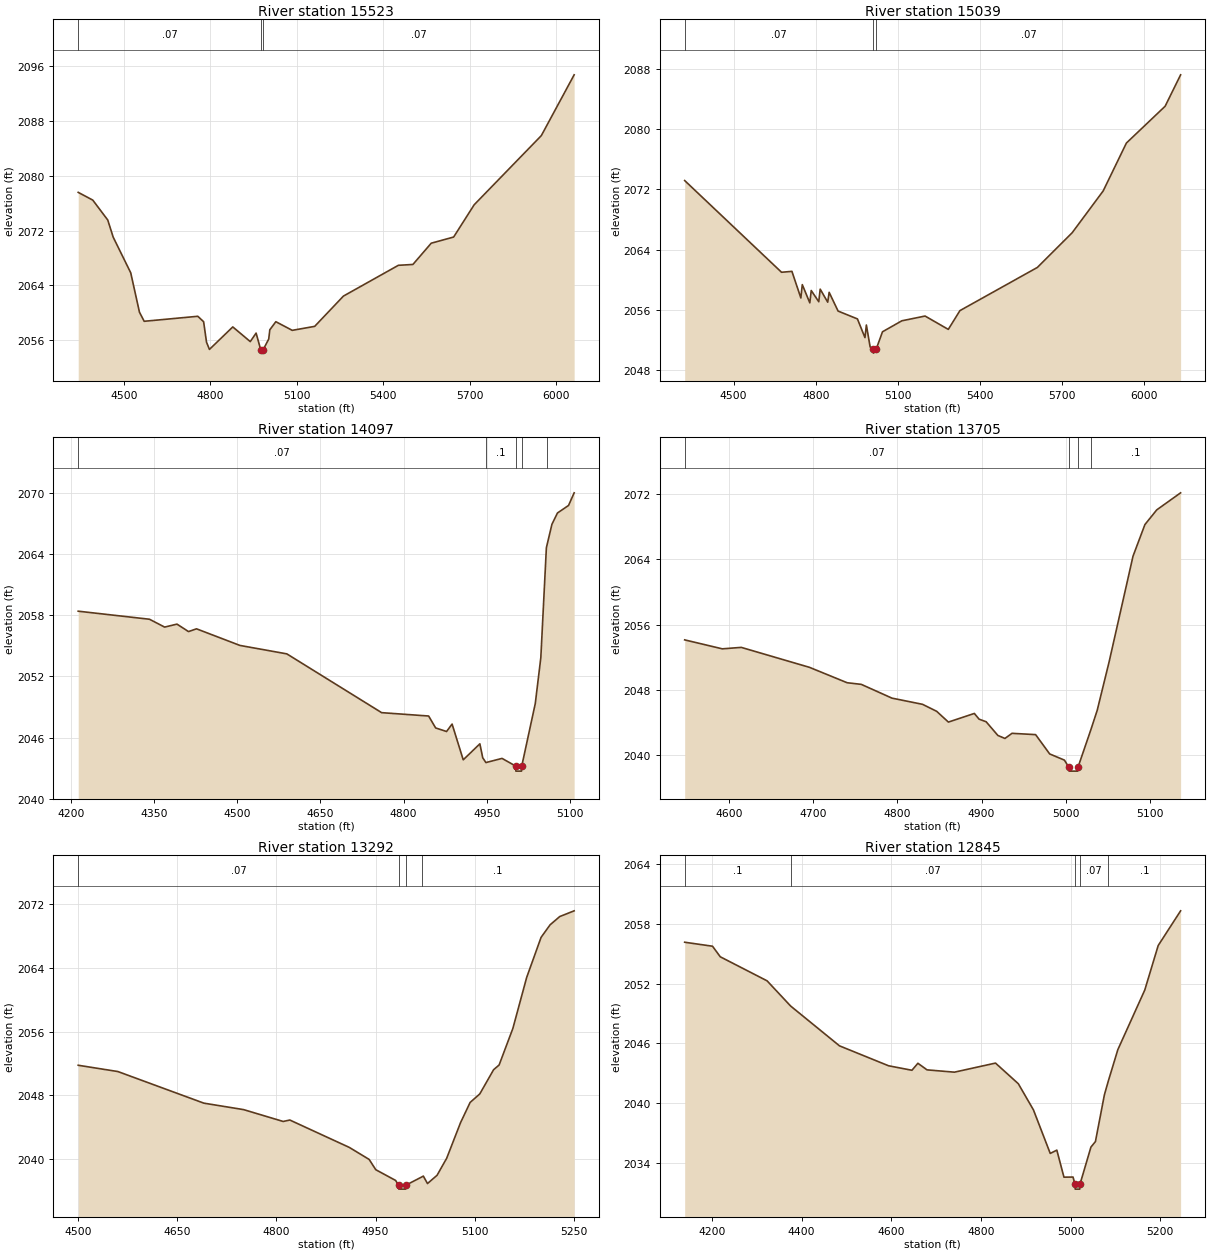
Type RM Length L Ch R = 1,15523,484,484,484
BEGIN DESCRIPTION:
Stream0190 33.0
END DESCRIPTION:
XS GIS Cut Line= 3
      1823425.04     13951074.99      1822775.00     13951175.00
      1821975.00     13951875.00
#Sta/Elev= 30
  4341.8 2077.56  4392.4 2076.43  4444.3 2073.53  4463.2 2071.03  4524.0 2065.84
  4554.3 2060.10  4570.7 2058.77  4756.7 2059.50  4776.9 2058.71  4787.0 2055.72
  4797.1 2054.67  4878.1 2057.95  4938.8 2055.81  4959.0 2057.05  4975.0 2054.63
  4975.5 2054.13  4983.5 2054.63  5002.8 2056.18  5006.6 2057.53  5027.5 2058.71
  5084.4 2057.45  5162.3 2058.03  5261.9 2062.44  5452.7 2066.93  5503.0 2067.05
  5566.6 2070.15  5644.4 2071.05  5715.6 2075.75  5948.6 2085.83  6062.5 2094.69
#Mann=3,-1,0
  4341.8    0.07       0  4975.0    0.05       0  4983.5    0.07       0
Bank Sta=4975,4983.5
Exp/Cntr=0.3,0.1

Type RM Length L Ch R = 1,15039,942,942,942
BEGIN DESCRIPTION:
Stream0190 32.0
END DESCRIPTION:
XS GIS Cut Line= 3
      1823325.01     13950925.00      1822675.00     13950725.00
      1821874.97     13951525.03
#Sta/Elev= 30
  4321.0 2073.15  4674.8 2060.98  4712.7 2061.10  4745.4 2057.57  4750.6 2059.34
  4778.1 2056.92  4783.3 2058.56  4810.8 2057.07  4816.0 2058.74  4843.5 2057.01
  4848.7 2058.32  4881.4 2055.83  4952.0 2054.79  4979.5 2052.31  4984.7 2053.98
  4998.5 2051.06  5010.2 2050.75  5010.7 2050.25  5020.3 2050.75  5043.5 2053.08
  5114.2 2054.54  5199.1 2055.17  5283.9 2053.40  5326.4 2055.89  5609.2 2061.62
  5736.5 2066.23  5849.6 2071.77  5934.5 2078.13  6075.9 2083.01  6132.5 2087.18
#Mann=3,-1,0
  4321.0    0.07       0  5010.2    0.05       0  5020.3    0.07       0
Bank Sta=5010.2,5020.3
Exp/Cntr=0.3,0.1

Type RM Length L Ch R = 1,14097,392,392,392
BEGIN DESCRIPTION:
Stream0190 31.0
END DESCRIPTION:
XS GIS Cut Line= 3
      1822775.00     13950475.00      1822272.75     13950067.47
      1822024.95     13950075.00
#Sta/Elev= 30
  4213.0 2058.41  4341.6 2057.62  4368.9 2056.85  4391.2 2057.14  4412.0 2056.41
  4426.4 2056.68  4504.7 2055.05  4589.4 2054.22  4760.4 2048.45  4845.2 2048.12
  4857.8 2046.95  4877.5 2046.60  4887.5 2047.33  4907.6 2043.82  4937.6 2045.39
  4942.8 2044.02  4948.5 2043.55  4977.6 2043.96  5002.1 2043.21  5002.6 2042.71
  5012.7 2042.71  5013.2 2043.21  5037.6 2049.35  5047.6 2053.86  5057.6 2064.64
  5059.2 2065.01  5067.6 2066.94  5077.6 2068.05  5097.6 2068.79  5107.7 2070.03
#Mann=5,-1,0
  4213.0    0.07       0  4948.5     0.1       0  5002.1    0.05       0
  5013.2     0.1       0  5059.2    0.07       0
Bank Sta=5002.1,5013.2
Exp/Cntr=0.3,0.1

Type RM Length L Ch R = 1,13705,413,413,413
BEGIN DESCRIPTION:
Stream0190 30.0
END DESCRIPTION:
XS GIS Cut Line= 3
      1822574.99     13950174.99      1822375.00     13949775.00
      1822275.01     13949675.01
#Sta/Elev= 30
  4547.7 2054.12  4592.4 2053.02  4614.8 2053.20  4695.8 2050.75  4740.5 2048.86
  4757.3 2048.66  4793.7 2046.97  4830.0 2046.21  4846.8 2045.35  4860.7 2044.03
  4891.5 2045.09  4897.1 2044.39  4905.5 2044.07  4919.4 2042.39  4927.8 2042.02
  4936.2 2042.65  4964.2 2042.49  4980.9 2040.12  4998.4 2039.36  5003.5 2038.51
  5004.0 2038.01  5014.1 2038.01  5014.6 2038.51  5029.9 2043.13  5037.3 2045.47
  5051.5 2051.45  5079.8 2064.39  5093.9 2068.27  5108.0 2070.08  5136.3 2072.17
#Mann=4,-1,0
  4547.7    0.07       0  5003.5    0.05       0  5014.6    0.07       0
  5029.9     0.1       0
Bank Sta=5003.5,5014.6
Exp/Cntr=0.3,0.1

Type RM Length L Ch R = 1,13292,447,447,447
BEGIN DESCRIPTION:
Stream0190 29.0
END DESCRIPTION:
XS GIS Cut Line= 3
      1822675.00     13950025.03      1822675.00     13949525.00
      1822475.03     13949375.02
#Sta/Elev= 30
  4500.3 2051.76  4560.3 2050.97  4690.3 2047.00  4750.3 2046.19  4810.3 2044.70
  4820.3 2044.88  4910.3 2041.44  4940.3 2039.93  4950.3 2038.64  4980.3 2037.29
  4984.7 2036.70  4985.2 2036.20  4995.4 2036.20  4995.9 2036.70  5020.1 2037.74
  5022.2 2037.84  5028.5 2036.90  5043.0 2037.94  5057.6 2040.09  5078.5 2044.55
  5093.0 2047.09  5107.6 2048.16  5128.5 2051.20  5136.8 2051.79  5157.6 2056.38
  5178.5 2062.79  5200.3 2067.83  5213.9 2069.40  5228.5 2070.44  5250.3 2071.16
#Mann=4,-1,0
  4500.3    0.07       0  4984.7    0.05       0  4995.9    0.07       0
  5020.1     0.1       0
Bank Sta=4984.7,4995.9
Exp/Cntr=0.3,0.1

Type RM Length L Ch R = 1,12845,486,486,486
BEGIN DESCRIPTION:
Stream0190 28.0
END DESCRIPTION:
XS GIS Cut Line= 3
      1823185.25     13950116.02      1823025.00     13949275.00
      1823025.00     13949024.95
#Sta/Elev= 30
  4139.1 2056.15  4201.2 2055.75  4218.5 2054.69  4322.9 2052.28  4375.5 2049.75
  4484.4 2045.76  4593.9 2043.76  4646.0 2043.31  4659.3 2044.01  4679.7 2043.35
  4740.8 2043.12  4832.4 2044.03  4883.3 2041.96  4917.0 2039.34  4954.5 2034.97
  4969.2 2035.30  4985.1 2032.59  5005.3 2032.60  5009.7 2031.89  5010.2 2031.39
  5020.4 2031.39  5020.9 2031.89  5045.3 2035.61  5055.3 2036.16  5075.3 2040.85
  5083.9 2042.21  5105.3 2045.38  5165.3 2051.35  5195.3 2055.82  5245.3 2059.30
#Mann=5,-1,0
  4139.1     0.1       0  4375.5    0.07       0  5009.7    0.05       0
  5020.9    0.07       0  5083.9     0.1       0
Bank Sta=5009.7,5020.9
Exp/Cntr=0.3,0.1