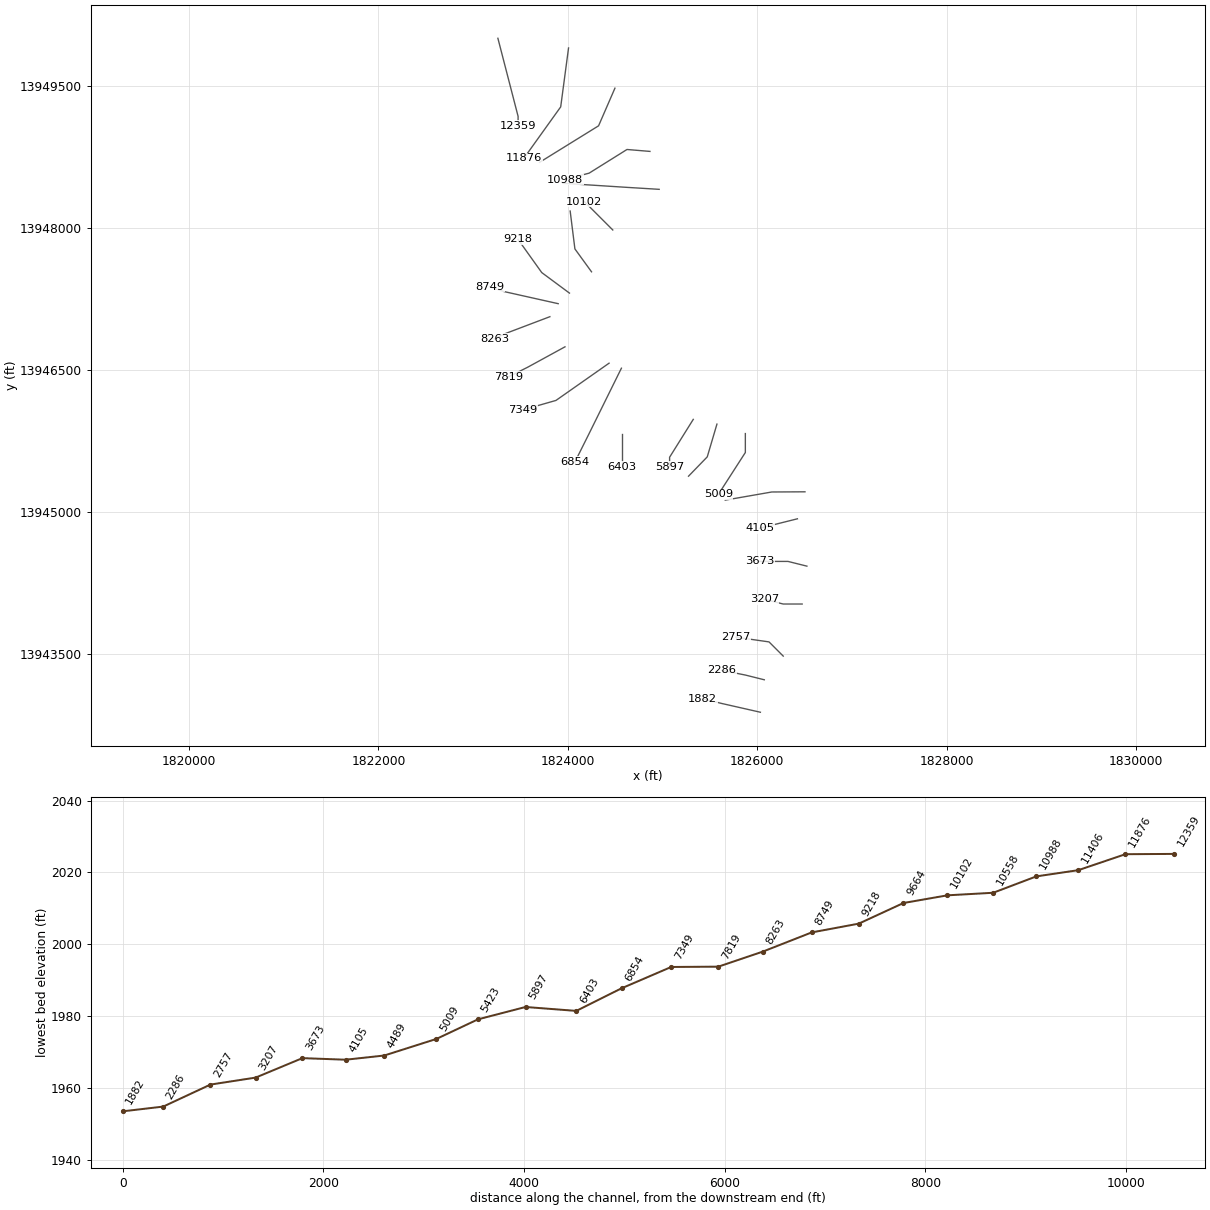
HEC-RAS study Stream0190.prj: Stream0190 Base Level Engineering

--- Stream0190.g01 (geometry) --- (continued)

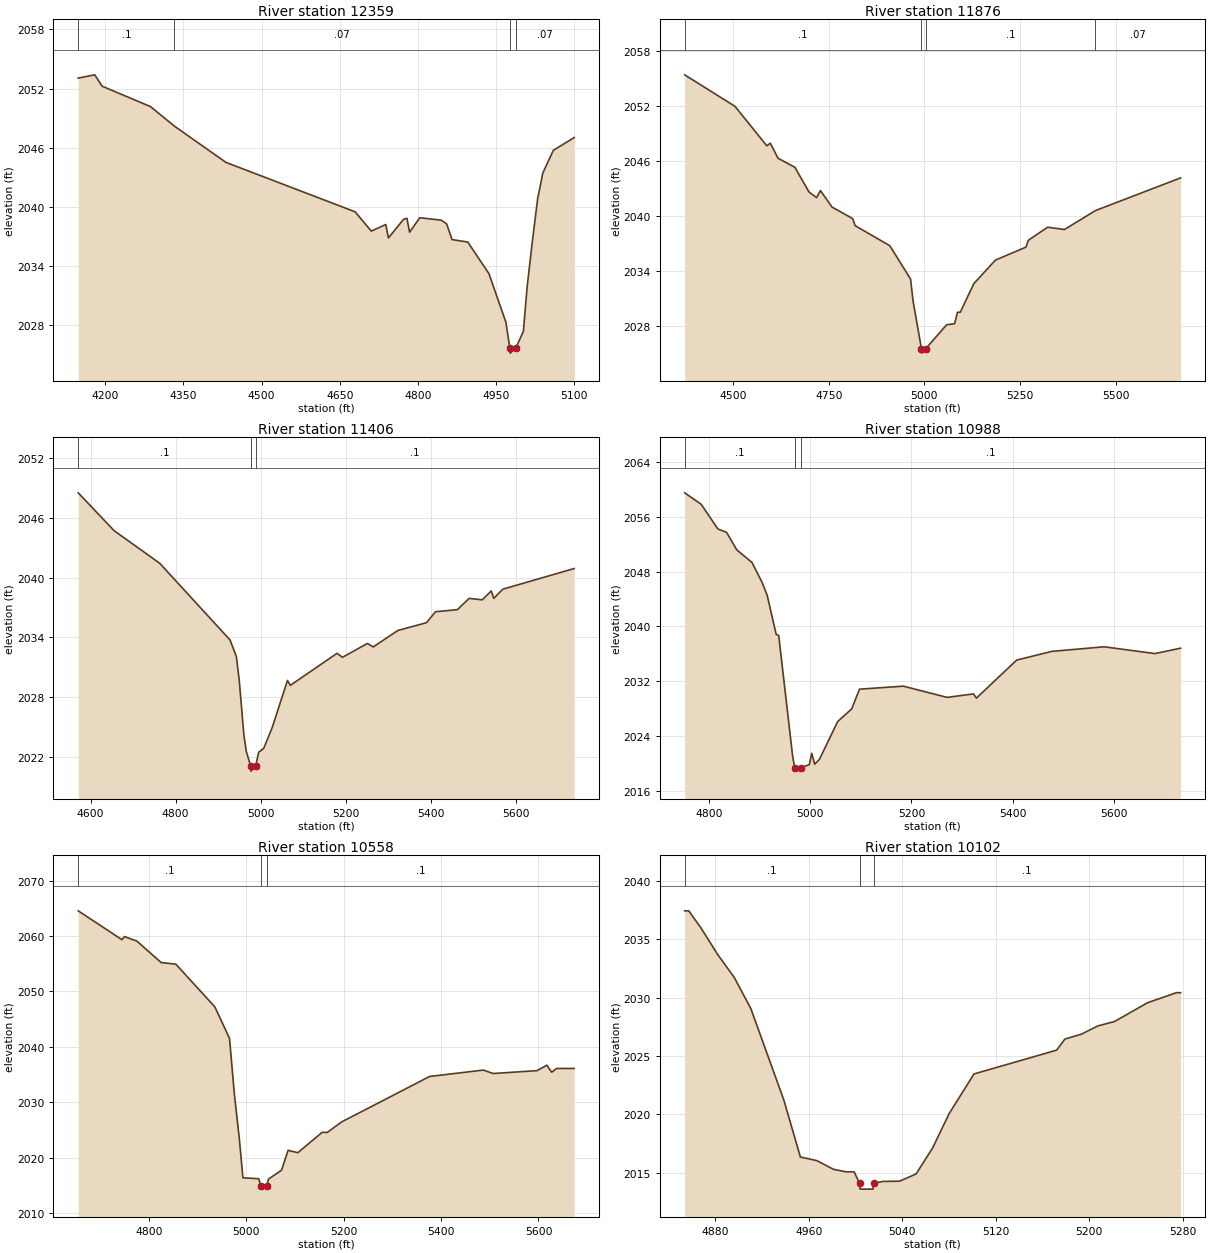
Type RM Length L Ch R = 1,12359,483,483,483
BEGIN DESCRIPTION:
Stream0190 27.0
END DESCRIPTION:
XS GIS Cut Line= 3
      1823261.71     13949999.37      1823475.00     13949175.00
      1823475.00     13949075.01
#Sta/Elev= 30
  4148.1 2053.06  4179.8 2053.39  4193.9 2052.24  4286.9 2050.16  4332.7 2048.18
  4431.5 2044.50  4679.4 2039.48  4710.4 2037.52  4738.2 2038.19  4743.3 2036.83
  4772.4 2038.72  4778.8 2038.82  4783.9 2037.41  4803.4 2038.88  4844.7 2038.63
  4854.9 2038.26  4865.3 2036.66  4895.5 2036.41  4936.1 2033.20  4968.6 2028.28
  4976.3 2025.63  4976.8 2025.13  4987.5 2025.63  5002.1 2027.32  5009.6 2031.95
  5019.6 2036.55  5029.6 2040.82  5039.6 2043.43  5059.6 2045.72  5099.6 2047.02
#Mann=4,-1,0
  4148.1     0.1       0  4332.7    0.07       0  4976.3    0.05       0
  4987.5    0.07       0
Bank Sta=4976.3,4987.5
Exp/Cntr=0.3,0.1

Type RM Length L Ch R = 1,11876,470,470,470
BEGIN DESCRIPTION:
Stream0190 26.0
END DESCRIPTION:
XS GIS Cut Line= 3
      1824007.87     13949897.02      1823925.00     13949275.00
      1823534.94     13948730.63
#Sta/Elev= 30
  4372.9 2055.40  4504.6 2051.96  4587.9 2047.65  4596.9 2047.95  4617.1 2046.30
  4661.1 2045.32  4697.8 2042.64  4717.9 2042.01  4728.0 2042.78  4758.3 2040.98
  4812.4 2039.72  4818.8 2038.95  4909.6 2036.76  4963.8 2033.12  4970.1 2030.78
  4992.1 2025.55  4992.6 2025.05  5003.7 2025.55  5058.1 2028.14  5079.0 2028.26
  5086.5 2029.51  5093.8 2029.51  5129.4 2032.64  5185.9 2035.20  5265.7 2036.61
  5271.9 2037.36  5322.2 2038.78  5366.4 2038.53  5447.0 2040.59  5670.1 2044.16
#Mann=4,-1,0
  4372.9     0.1       0  4992.1    0.05       0  5003.7     0.1       0
  5447.0    0.07       0
Bank Sta=4992.1,5003.7
Exp/Cntr=0.3,0.1

Type RM Length L Ch R = 1,11406,418,418,418
BEGIN DESCRIPTION:
Stream0190 25.0
END DESCRIPTION:
XS GIS Cut Line= 3
      1824497.78     13949472.59      1824325.00     13949075.00
      1823701.46     13948689.10
#Sta/Elev= 30
  4571.0 2048.50  4655.6 2044.70  4762.7 2041.44  4928.2 2033.75  4943.2 2032.07
  4950.0 2029.63  4960.9 2024.17  4966.6 2022.55  4976.9 2021.10  4977.4 2020.60
  4988.5 2021.10  4995.5 2022.49  5007.4 2022.88  5027.6 2024.99  5063.3 2029.69
  5070.1 2029.20  5180.0 2032.41  5192.7 2032.01  5251.5 2033.40  5265.1 2033.05
  5323.0 2034.70  5390.4 2035.48  5411.6 2036.58  5463.2 2036.79  5490.8 2037.92
  5521.6 2037.77  5542.8 2038.67  5548.7 2037.92  5570.0 2038.84  5737.8 2040.91
#Mann=3,-1,0
  4571.0     0.1       0  4976.9    0.05       0  4988.5     0.1       0
Bank Sta=4976.9,4988.5
Exp/Cntr=0.3,0.1

Type RM Length L Ch R = 1,10988,430,430,430
BEGIN DESCRIPTION:
Stream0190 24.0
END DESCRIPTION:
XS GIS Cut Line= 4
      1824867.54     13948804.73      1824625.00     13948825.00
      1824225.00     13948575.00      1823968.75     13948507.79
#Sta/Elev= 30
  4752.0 2059.52  4784.7 2057.84  4817.5 2054.25  4834.8 2053.75  4854.9 2051.19
  4885.0 2049.35  4905.1 2046.42  4915.1 2044.54  4932.8 2038.85  4937.8 2038.69
  4965.3 2021.07  4969.4 2019.37  4969.9 2018.87  4981.3 2019.37  4998.3 2019.82
  5003.1 2021.47  5008.9 2019.88  5018.4 2020.60  5054.3 2026.11  5082.1 2027.96
  5097.4 2030.84  5184.1 2031.28  5270.7 2029.64  5322.6 2030.15  5328.5 2029.54
  5408.1 2035.09  5477.4 2036.36  5580.8 2037.03  5681.4 2036.04  5732.0 2036.83
#Mann=3,-1,0
  4752.0     0.1       0  4969.4    0.05       0  4981.3     0.1       0
Bank Sta=4969.4,4981.3
Exp/Cntr=0.3,0.1

Type RM Length L Ch R = 1,10558,456,456,456
BEGIN DESCRIPTION:
Stream0190 23.0
END DESCRIPTION:
XS GIS Cut Line= 3
      1824965.01     13948404.25      1824625.00     13948425.00
      1823949.02     13948468.26
#Sta/Elev= 30
  4655.3 2064.55  4745.1 2059.34  4750.1 2059.90  4775.5 2059.10  4825.6 2055.21
  4855.7 2054.92  4935.8 2047.21  4965.9 2041.52  4975.9 2031.39  4985.9 2023.52
  4993.4 2016.35  5026.0 2016.19  5030.1 2014.81  5030.6 2014.31  5042.0 2014.81
  5046.0 2016.13  5072.7 2017.73  5086.1 2021.31  5106.2 2020.89  5156.3 2024.58
  5166.3 2024.53  5196.4 2026.46  5376.7 2034.65  5486.9 2035.80  5507.0 2035.18
  5597.2 2035.70  5617.2 2036.68  5627.2 2035.42  5637.3 2036.10  5673.3 2036.09
#Mann=3,-1,0
  4655.3     0.1       0  5030.1    0.05       0  5042.0     0.1       0
Bank Sta=5030.1,5042
Exp/Cntr=0.3,0.1

Type RM Length L Ch R = 1,10102,438,438,438
BEGIN DESCRIPTION:
Stream0190 22.0
END DESCRIPTION:
XS GIS Cut Line= 3
      1824475.00     13947975.00      1824375.00     13948075.00
      1824174.98     13948275.02
#Sta/Elev= 30
  4853.8 2037.43  4857.3 2037.43  4867.9 2035.94  4882.1 2033.68  4896.2 2031.73
  4910.4 2029.06  4938.7 2021.21  4952.8 2016.35  4966.9 2016.04  4981.1 2015.30
  4991.7 2015.08  4998.8 2015.08  5003.4 2014.10  5003.9 2013.60  5014.9 2013.60
  5015.4 2014.10  5023.5 2014.26  5037.7 2014.28  5051.8 2014.90  5065.9 2017.12
  5080.1 2020.07  5101.3 2023.46  5172.0 2025.50  5179.1 2026.45  5193.2 2026.87
  5207.4 2027.58  5221.5 2027.95  5249.8 2029.56  5274.5 2030.42  5278.1 2030.42
#Mann=3,-1,0
  4853.8     0.1       0  5003.4    0.05       0  5015.4     0.1       0
Bank Sta=5003.4,5015.4
Exp/Cntr=0.3,0.1

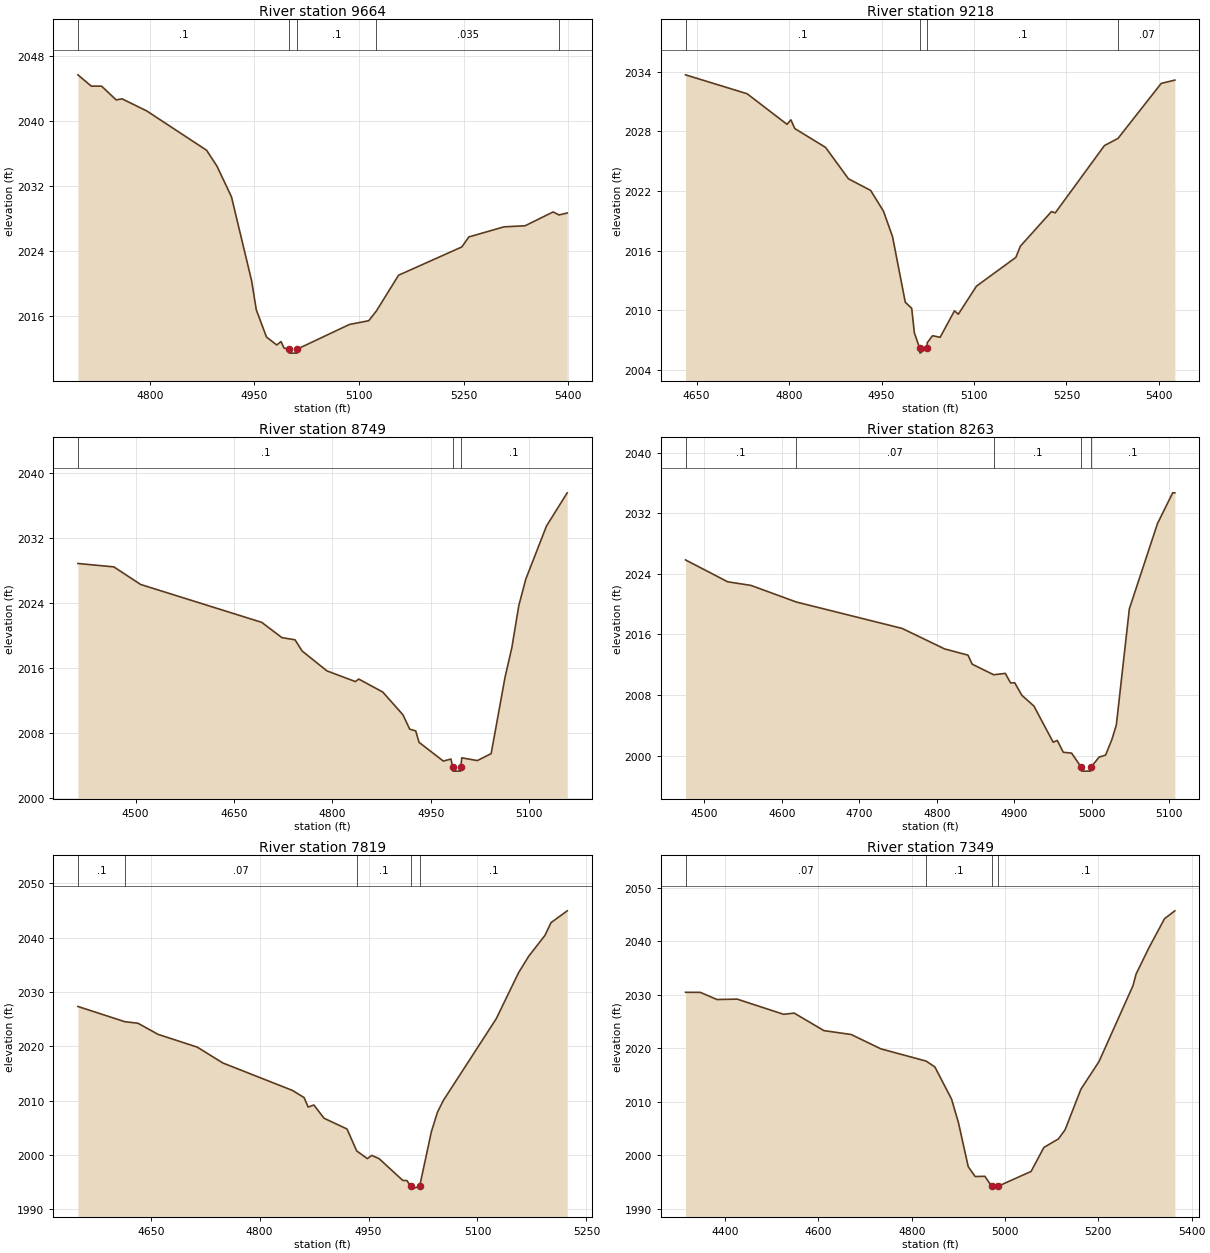
Type RM Length L Ch R = 1,9664,446,446,446
BEGIN DESCRIPTION:
Stream0190 21.0
END DESCRIPTION:
XS GIS Cut Line= 3
      1824250.49     13947533.21      1824075.00     13947775.00
      1824025.00     13948175.03
#Sta/Elev= 30
  4696.7 2045.64  4716.0 2044.25  4730.7 2044.25  4751.6 2042.56  4760.1 2042.69
  4795.6 2041.20  4881.4 2036.37  4896.1 2034.44  4917.0 2030.66  4946.0 2020.31
  4952.6 2016.78  4967.2 2013.44  4981.9 2012.46  4988.1 2012.88  4992.4 2012.08
  4999.5 2011.96  5000.0 2011.46  5011.0 2011.46  5011.5 2011.96  5086.2 2014.98
  5113.9 2015.44  5124.8 2016.63  5156.7 2021.03  5247.4 2024.50  5257.5 2025.73
  5307.9 2026.97  5338.1 2027.10  5378.4 2028.80  5386.8 2028.43  5398.6 2028.67
#Mann=5,-1,0
  4696.7     0.1       0  4999.5    0.05       0  5011.5     0.1       0
  5124.8   0.035       0  5386.8     0.1       0
Bank Sta=4999.5,5011.5
Exp/Cntr=0.3,0.1

Type RM Length L Ch R = 1,9218,469,469,469
BEGIN DESCRIPTION:
Stream0190 20.0
END DESCRIPTION:
XS GIS Cut Line= 3
      1824017.52     13947308.36      1823725.00     13947525.00
      1823475.01     13947874.98
#Sta/Elev= 30
  4631.9 2033.67  4731.9 2031.77  4796.6 2028.70  4802.9 2029.15  4809.3 2028.27
  4859.2 2026.38  4896.4 2023.22  4932.3 2022.06  4953.1 2019.98  4967.8 2017.43
  4988.6 2010.82  4999.0 2010.21  5003.3 2007.75  5011.9 2006.21  5012.4 2005.71
  5024.1 2006.21  5024.2 2006.75  5032.8 2007.46  5045.1 2007.30  5068.4 2009.96
  5074.6 2009.62  5104.1 2012.44  5168.0 2015.33  5175.3 2016.45  5225.7 2019.93
  5231.9 2019.80  5311.7 2026.56  5333.7 2027.28  5403.9 2032.81  5426.0 2033.14
#Mann=4,-1,0
  4631.9     0.1       0  5011.9    0.05       0  5024.1     0.1       0
  5333.7    0.07       0
Bank Sta=5011.9,5024.1
Exp/Cntr=0.3,0.1

Type RM Length L Ch R = 1,8749,486,486,486
BEGIN DESCRIPTION:
Stream0190 19.0
END DESCRIPTION:
XS GIS Cut Line= 3
      1823898.43     13947196.76      1823325.00     13947325.00
      1823175.01     13947375.00
#Sta/Elev= 30
  4412.1 2028.87  4466.9 2028.45  4507.8 2026.28  4692.3 2021.61  4723.0 2019.73
  4743.0 2019.46  4753.8 2018.08  4791.6 2015.63  4835.0 2014.31  4840.1 2014.62
  4876.7 2013.02  4907.5 2010.21  4917.7 2008.45  4926.9 2008.23  4932.0 2006.82
  4969.0 2004.51  4980.6 2004.76  4983.3 2003.77  4983.8 2003.27  4995.1 2003.27
  4995.6 2003.77  4997.1 2004.91  5020.8 2004.57  5041.9 2005.43  5062.9 2014.79
  5073.5 2018.53  5084.0 2023.68  5094.6 2026.93  5126.2 2033.49  5157.8 2037.58
#Mann=3,-1,0
  4412.1     0.1       0  4983.3    0.05       0  4995.6     0.1       0
Bank Sta=4983.3,4995.6
Exp/Cntr=0.3,0.1

Type RM Length L Ch R = 1,8263,444,444,444
BEGIN DESCRIPTION:
Stream0190 18.0
END DESCRIPTION:
XS GIS Cut Line= 3
      1823810.81     13947059.32      1823325.00     13946875.00
      1823225.00     13946825.00
#Sta/Elev= 30
  4475.8 2025.84  4530.2 2022.95  4560.3 2022.47  4618.7 2020.28  4755.3 2016.79
  4810.2 2014.08  4840.3 2013.26  4845.7 2012.07  4873.4 2010.67  4888.4 2010.85
  4895.3 2009.59  4900.6 2009.61  4909.8 2007.96  4925.4 2006.53  4950.2 2001.76
  4955.5 2001.99  4963.3 2000.43  4974.0 2000.32  4986.5 1998.44  4987.0 1997.94
  4998.4 1997.94  4998.9 1998.44  5009.4 1999.79  5017.8 2000.05  5026.1 2002.16
  5031.7 2004.04  5048.5 2019.38  5084.8 2030.64  5104.4 2034.70  5107.2 2034.70
#Mann=5,-1,0
  4475.8     0.1       0  4618.7    0.07       0  4873.4     0.1       0
  4986.5    0.05       0  4998.9     0.1       0
Bank Sta=4986.5,4998.9
Exp/Cntr=0.3,0.1

Type RM Length L Ch R = 1,7819,470,470,470
BEGIN DESCRIPTION:
Stream0190 17.0
END DESCRIPTION:
XS GIS Cut Line= 3
      1823970.22     13946741.08      1823575.00     13946525.00
      1823375.04     13946425.02
#Sta/Elev= 30
  4549.6 2027.34  4614.2 2024.54  4632.4 2024.25  4660.0 2022.21  4714.0 2019.86
  4749.3 2016.94  4844.9 2011.91  4861.1 2010.59  4866.8 2008.84  4874.7 2009.21
  4888.6 2006.78  4920.3 2004.80  4933.6 2000.77  4948.3 1999.35  4954.4 1999.94
  4964.5 1999.35  4997.2 1995.33  5002.8 1995.33  5007.8 1994.24  5008.3 1993.74
  5020.3 1994.24  5036.4 2004.26  5044.8 2007.87  5053.1 2010.08  5125.8 2025.08
  5156.6 2033.55  5170.5 2036.57  5192.9 2040.41  5201.3 2042.76  5223.6 2044.93
#Mann=5,-1,0
  4549.6     0.1       0  4614.2    0.07       0  4933.6     0.1       0
  5007.8    0.05       0  5020.3     0.1       0
Bank Sta=5007.8,5020.3
Exp/Cntr=0.3,0.1

Type RM Length L Ch R = 1,7349,495,495,495
BEGIN DESCRIPTION:
Stream0190 16.0
END DESCRIPTION:
XS GIS Cut Line= 3
      1824435.80     13946568.35      1823875.00     13946175.00
      1823525.00     13946075.00
#Sta/Elev= 30
  4315.0 2030.49  4346.7 2030.48  4382.5 2029.14  4425.9 2029.21  4525.4 2026.37
  4548.0 2026.60  4611.7 2023.32  4670.2 2022.59  4733.7 2019.91  4831.0 2017.61
  4849.6 2016.51  4885.4 2010.49  4900.2 2006.06  4921.1 1997.85  4935.9 1996.01
  4956.8 1996.05  4971.5 1994.15  4972.0 1993.65  4984.0 1994.15  5055.9 1996.97
  5083.2 2001.45  5114.4 2003.05  5128.7 2004.75  5162.5 2012.33  5201.5 2017.54
  5274.3 2031.74  5280.8 2033.89  5308.1 2038.77  5341.9 2044.27  5364.0 2045.74
#Mann=4,-1,0
  4315.0    0.07       0  4831.0     0.1       0  4971.5    0.05       0
  4984.0     0.1       0
Bank Sta=4971.5,4984
Exp/Cntr=0.3,0.1

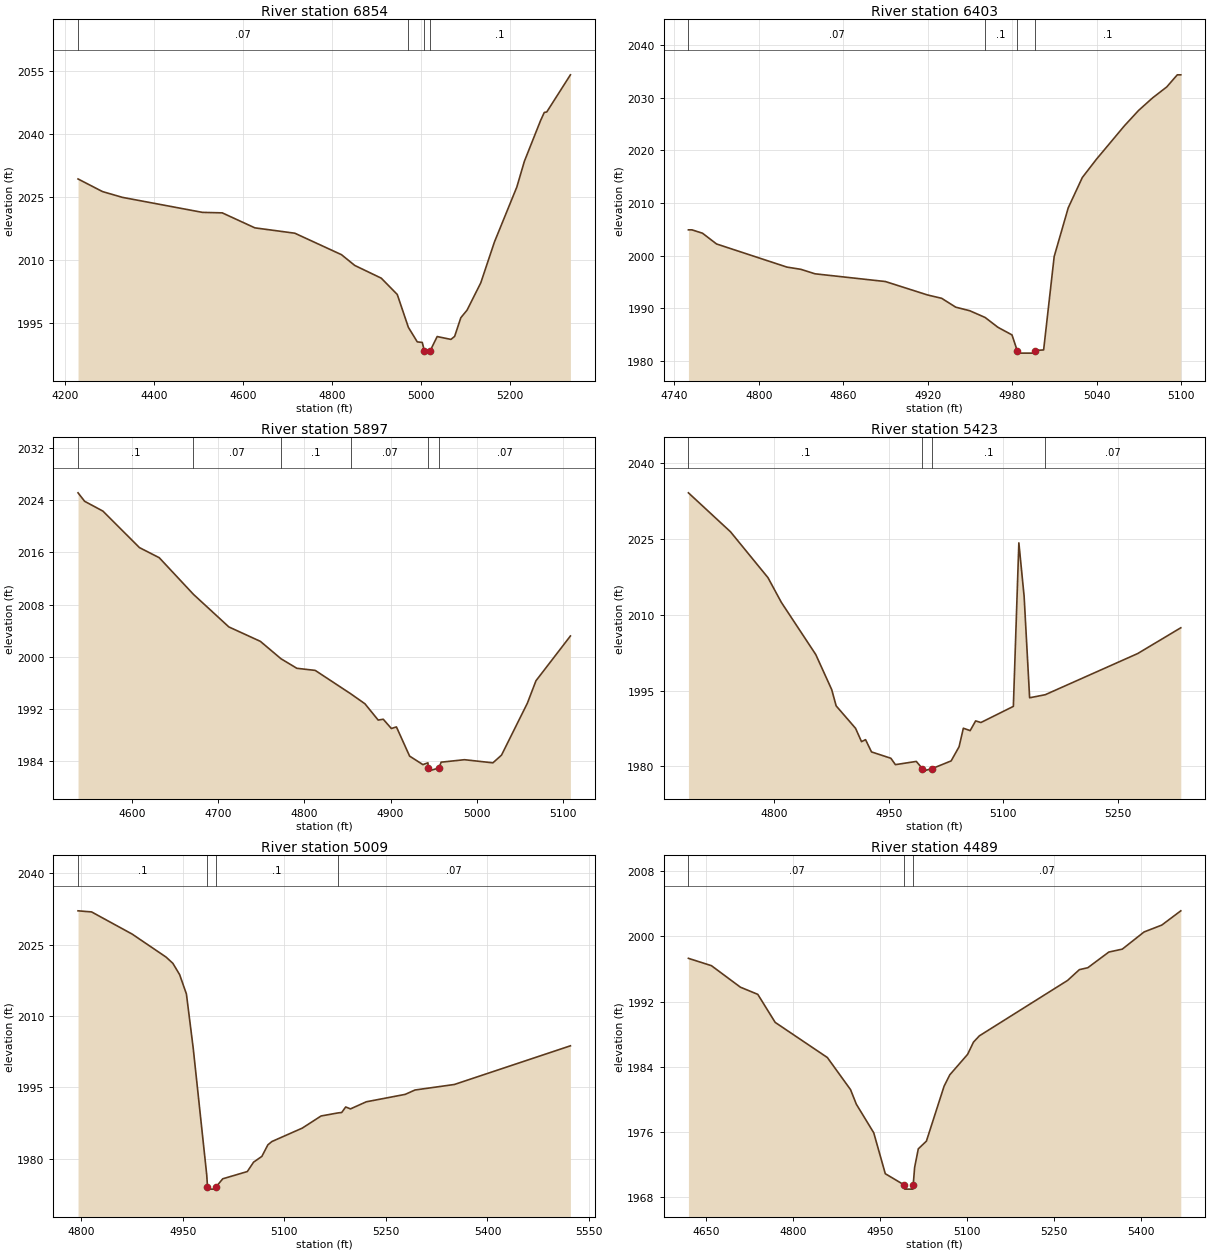
Type RM Length L Ch R = 1,6854,451,451,451
BEGIN DESCRIPTION:
Stream0190 15.0
END DESCRIPTION:
XS GIS Cut Line= 3
      1824566.15     13946515.30      1824225.00     13945825.00
      1824075.00     13945525.01
#Sta/Elev= 30
  4230.0 2029.31  4284.8 2026.30  4329.7 2024.91  4509.2 2021.33  4553.8 2021.21
  4627.0 2017.63  4716.7 2016.35  4821.5 2011.22  4851.3 2008.65  4910.8 2005.61
  4946.7 2001.72  4971.6 1993.88  4991.6 1990.40  5002.8 1990.26  5007.7 1988.21
  5008.2 1987.71  5020.3 1988.21  5036.3 1991.67  5067.1 1990.99  5075.5 1991.71
  5089.4 1996.17  5103.4 1997.98  5134.2 2004.51  5164.9 2014.27  5215.2 2027.41
  5232.0 2033.51  5268.3 2043.23  5276.7 2045.19  5282.3 2045.31  5335.4 2054.18
#Mann=4,-1,0
  4230.0    0.07       0  4971.6     0.1       0  5007.7    0.05       0
  5020.3     0.1       0
Bank Sta=5007.7,5020.3
Exp/Cntr=0.3,0.1

Type RM Length L Ch R = 1,6403,506,506,506
BEGIN DESCRIPTION:
Stream0190 14.0
END DESCRIPTION:
XS GIS Cut Line= 3
      1824575.00     13945825.00      1824575.00     13945575.00
      1824575.00     13945475.00
#Sta/Elev= 30
  4749.9 2004.89  4752.4 2004.89  4759.9 2004.25  4769.9 2002.20  4819.9 1997.80
  4829.9 1997.37  4839.9 1996.52  4889.9 1995.05  4919.9 1992.49  4929.9 1991.86
  4939.9 1990.17  4949.9 1989.49  4960.8 1988.21  4969.9 1986.34  4979.9 1984.89
  4983.6 1981.92  4984.1 1981.42  4995.7 1981.42  4996.2 1981.92  5002.4 1982.03
  5009.9 1999.81  5019.9 2009.09  5029.9 2014.85  5039.9 2018.32  5059.9 2024.72
  5069.9 2027.62  5079.9 2030.02  5089.9 2032.09  5097.4 2034.40  5099.9 2034.40
#Mann=4,-1,0
  4749.9    0.07       0  4960.8     0.1       0  4983.6    0.05       0
  4996.2     0.1       0
Bank Sta=4983.6,4996.2
Exp/Cntr=0.3,0.1

Type RM Length L Ch R = 1,5897,474,474,474
BEGIN DESCRIPTION:
Stream0190 13.0
END DESCRIPTION:
XS GIS Cut Line= 3
      1825325.00     13945975.00      1825075.00     13945575.00
      1825075.00     13945475.00
#Sta/Elev= 30
  4537.1 2025.14  4544.8 2023.84  4566.0 2022.34  4608.4 2016.75  4631.4 2015.20
  4671.1 2009.59  4712.2 2004.60  4748.8 2002.39  4772.8 1999.72  4791.2 1998.26
  4812.5 1997.94  4853.7 1994.36  4870.2 1992.83  4885.6 1990.33  4891.5 1990.46
  4900.9 1989.04  4906.8 1989.28  4922.1 1984.81  4937.5 1983.51  4943.4 1983.78
  4943.5 1983.01  4944.0 1982.51  4956.2 1983.01  4958.7 1983.88  4985.8 1984.26
  5018.8 1983.78  5028.8 1984.96  5058.8 1992.91  5068.8 1996.35  5108.8 2003.21
#Mann=6,-1,0
  4537.1     0.1       0  4671.1    0.07       0  4772.8     0.1       0
  4853.7    0.07       0  4943.5    0.05       0  4956.2    0.07       0
Bank Sta=4943.5,4956.2
Exp/Cntr=0.3,0.1

Type RM Length L Ch R = 1,5423,414,414,414
BEGIN DESCRIPTION:
Stream0190 12.0
END DESCRIPTION:
XS GIS Cut Line= 3
      1825574.99     13945924.97      1825472.80     13945579.17
      1825274.97     13945374.97
#Sta/Elev= 30
  4687.5 2034.09  4742.6 2026.39  4791.7 2017.32  4809.2 2012.44  4854.3 2002.12
  4875.2 1995.18  4881.0 1991.97  4906.4 1987.54  4914.2 1984.90  4919.5 1985.29
  4927.3 1982.87  4952.7 1981.61  4958.6 1980.35  4986.0 1980.99  4993.9 1979.57
  4994.4 1979.07  5006.7 1979.57  5031.6 1981.09  5042.0 1983.89  5047.6 1987.55
  5056.5 1987.08  5063.7 1989.00  5070.6 1988.68  5113.1 1991.87  5120.3 2024.20
  5127.2 2013.62  5134.4 1993.57  5154.9 1994.18  5275.9 2002.31  5332.4 2007.41
#Mann=4,-1,0
  4687.5     0.1       0  4993.9    0.05       0  5006.7     0.1       0
  5154.9    0.07       0
Bank Sta=4993.9,5006.7
Exp/Cntr=0.3,0.1

Type RM Length L Ch R = 1,5009,520,520,520
BEGIN DESCRIPTION:
Stream0190 11.0
END DESCRIPTION:
XS GIS Cut Line= 3
      1825875.00     13945825.03      1825875.00     13945625.00
      1825589.79     13945182.12
#Sta/Elev= 30
  4795.6 2032.13  4815.6 2031.90  4875.6 2027.23  4925.6 2022.40  4935.6 2021.09
  4945.6 2018.71  4955.6 2014.64  4965.6 2003.27  4985.6 1976.57  4986.7 1974.12
  4987.2 1973.62  4999.0 1973.62  4999.5 1974.12  5009.2 1975.79  5045.5 1977.32
  5054.7 1979.29  5067.0 1980.51  5075.8 1982.93  5081.8 1983.63  5126.5 1986.44
  5154.4 1989.00  5179.2 1989.64  5184.8 1989.73  5190.7 1990.89  5197.8 1990.49
  5221.1 1991.98  5278.5 1993.54  5293.0 1994.46  5351.1 1995.62  5522.4 2003.75
#Mann=4,-1,0
  4795.6     0.1       0  4986.7    0.05       0  4999.5     0.1       0
  5179.2    0.07       0
Bank Sta=4986.7,4999.5
Exp/Cntr=0.3,0.1

Type RM Length L Ch R = 1,4489,384,384,384
BEGIN DESCRIPTION:
Stream0190 10.0
END DESCRIPTION:
XS GIS Cut Line= 3
      1826504.70     13945209.99      1826154.45     13945208.17
      1825662.65     13945122.30
#Sta/Elev= 30
  4619.6 1997.32  4659.3 1996.42  4709.3 1993.78  4739.3 1992.90  4769.3 1989.46
  4859.3 1985.15  4899.3 1981.21  4909.3 1979.42  4939.3 1975.92  4959.3 1970.89
  4992.2 1969.50  4992.7 1969.00  5006.9 1969.00  5007.4 1969.50  5009.9 1971.67
  5016.2 1973.94  5030.2 1974.89  5060.7 1981.63  5070.6 1983.03  5101.3 1985.54
  5111.4 1987.04  5121.6 1987.81  5273.8 1994.61  5294.1 1995.93  5308.7 1996.17
  5344.9 1998.09  5368.2 1998.45  5405.8 2000.56  5436.3 2001.40  5469.1 2003.15
#Mann=3,-1,0
  4619.6    0.07       0  4992.2    0.05       0  5007.4    0.07       0
Bank Sta=4992.2,5007.4
Exp/Cntr=0.3,0.1

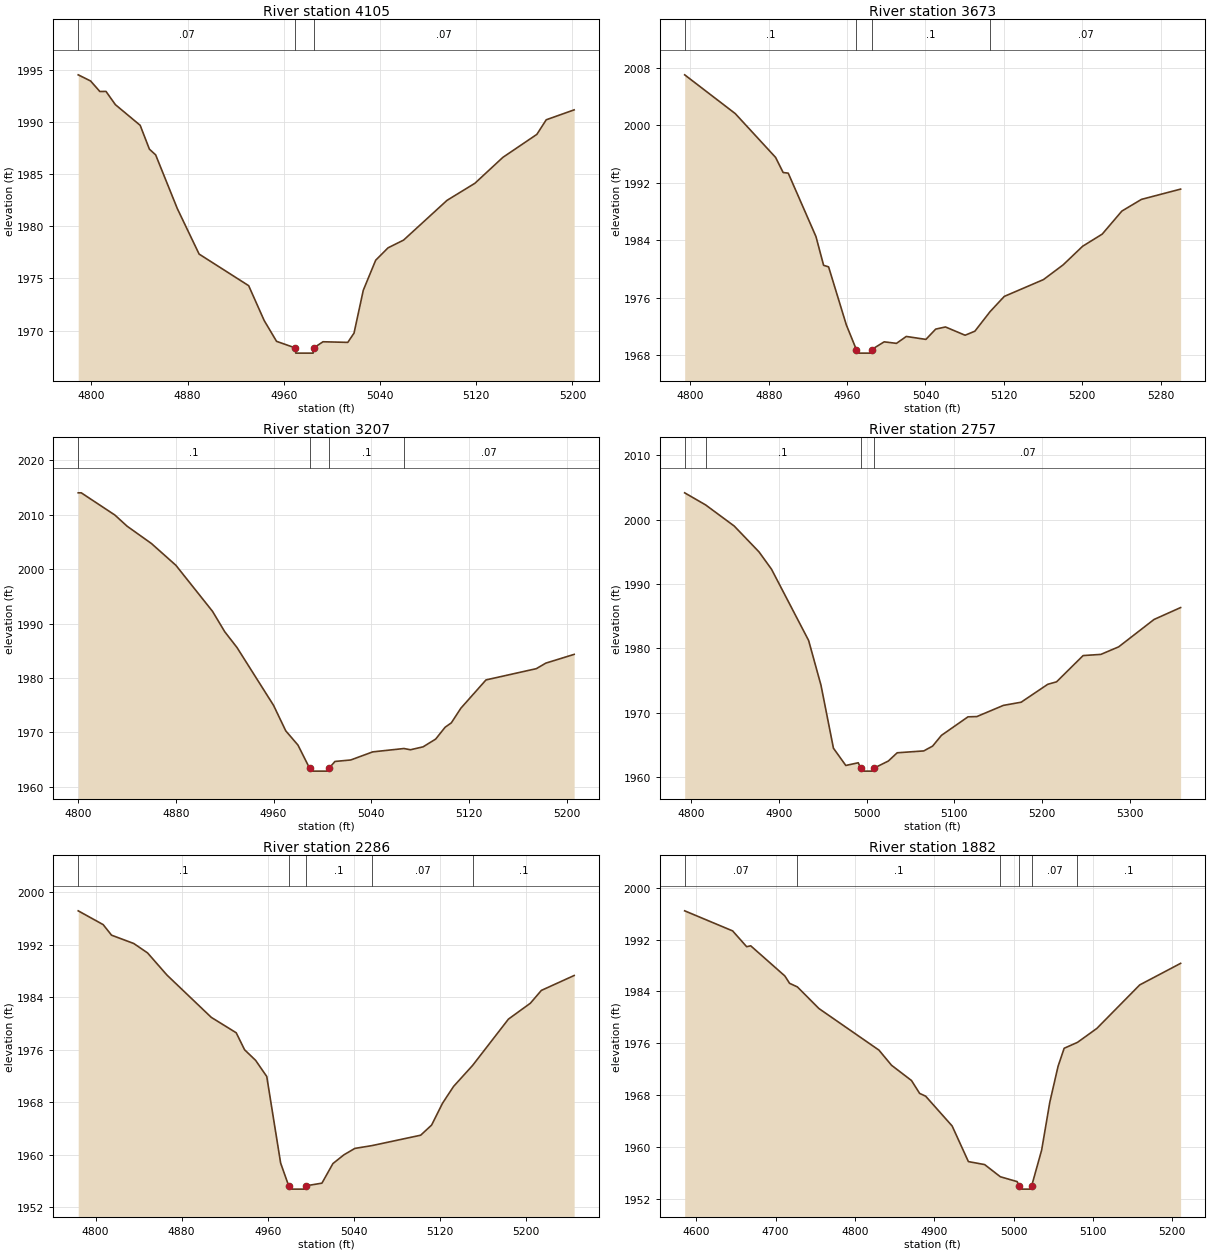
Type RM Length L Ch R = 1,4105,432,432,432
BEGIN DESCRIPTION:
Stream0190 9.0
END DESCRIPTION:
XS GIS Cut Line= 3
      1826424.96     13944924.99      1826225.00     13944875.00
      1826024.97     13944824.99
#Sta/Elev= 30
  4789.1 1994.52  4799.4 1993.93  4807.1 1992.92  4812.2 1992.93  4820.0 1991.66
  4840.6 1989.68  4848.3 1987.39  4853.5 1986.84  4871.5 1981.69  4889.6 1977.33
  4930.8 1974.30  4943.7 1970.96  4954.0 1968.96  4969.5 1968.33  4970.0 1967.83
  4984.4 1967.83  4984.9 1968.33  4992.6 1968.92  5013.2 1968.86  5018.4 1969.75
  5026.1 1973.86  5036.4 1976.74  5046.7 1977.93  5059.6 1978.67  5095.7 1982.48
  5118.9 1984.12  5142.1 1986.60  5170.4 1988.81  5178.2 1990.21  5201.4 1991.16
#Mann=3,-1,0
  4789.1    0.07       0  4969.5    0.05       0  4984.9    0.07       0
Bank Sta=4969.5,4984.9
Exp/Cntr=0.3,0.1

Type RM Length L Ch R = 1,3673,466,466,466
BEGIN DESCRIPTION:
Stream0190 8.0
END DESCRIPTION:
XS GIS Cut Line= 3
      1826525.04     13944424.99      1826325.00     13944475.00
      1826025.00     13944475.00
#Sta/Elev= 30
  4794.2 2006.99  4845.8 2001.60  4887.0 1995.50  4894.7 1993.40  4899.9 1993.31
  4928.2 1984.49  4936.0 1980.49  4941.1 1980.27  4959.2 1972.20  4969.4 1968.77
  4969.9 1968.27  4984.6 1968.27  4985.1 1968.77  4997.8 1969.84  5010.4 1969.63
  5020.4 1970.59  5040.4 1970.18  5050.4 1971.61  5060.4 1971.91  5080.4 1970.76
  5090.4 1971.32  5105.9 1974.04  5120.4 1976.16  5160.4 1978.50  5180.4 1980.54
  5200.4 1983.14  5220.4 1984.83  5240.4 1988.03  5260.4 1989.66  5300.4 1991.09
#Mann=4,-1,0
  4794.2     0.1       0  4969.4    0.05       0  4985.1     0.1       0
  5105.9    0.07       0
Bank Sta=4969.4,4985.1
Exp/Cntr=0.3,0.1

Type RM Length L Ch R = 1,3207,450,450,450
BEGIN DESCRIPTION:
Stream0190 7.0
END DESCRIPTION:
XS GIS Cut Line= 3
      1826475.00     13944025.00      1826275.00     13944025.00
      1826074.95     13944075.01
#Sta/Elev= 30
  4800.0 2014.05  4802.5 2014.05  4830.0 2009.97  4840.0 2007.92  4860.0 2004.72
  4880.0 2000.72  4910.0 1992.25  4920.0 1988.50  4930.0 1985.61  4960.0 1974.95
  4970.0 1970.26  4980.0 1967.64  4989.6 1963.35  4990.1 1962.85  5004.8 1962.85
  5005.3 1963.35  5010.3 1964.63  5023.2 1964.90  5041.2 1966.39  5066.8 1967.01
  5072.1 1966.78  5082.5 1967.32  5092.8 1968.75  5100.5 1970.92  5105.6 1971.73
  5113.4 1974.42  5134.0 1979.63  5175.2 1981.70  5183.0 1982.72  5206.2 1984.33
#Mann=4,-1,0
  4800.0     0.1       0  4989.6    0.05       0  5005.3     0.1       0
  5066.8    0.07       0
Bank Sta=4989.6,5005.3
Exp/Cntr=0.3,0.1

Type RM Length L Ch R = 1,2757,471,471,471
BEGIN DESCRIPTION:
Stream0190 6.0
END DESCRIPTION:
XS GIS Cut Line= 3
      1826274.98     13943475.02      1826125.00     13943625.00
      1825774.96     13943675.01
#Sta/Elev= 30
  4792.5 2004.16  4816.4 2002.28  4849.0 1999.00  4877.3 1994.98  4891.5 1992.30
  4933.9 1981.21  4948.0 1974.25  4962.2 1964.47  4976.3 1961.79  4990.5 1962.21
  4993.1 1961.41  4993.6 1960.91  5008.5 1960.91  5009.0 1961.41  5024.8 1962.48
  5034.9 1963.76  5065.2 1964.05  5075.3 1964.80  5085.4 1966.47  5115.7 1969.35
  5125.8 1969.39  5156.1 1971.13  5176.3 1971.62  5206.6 1974.40  5216.7 1974.79
  5247.0 1978.87  5267.2 1979.05  5287.5 1980.22  5327.9 1984.48  5358.2 1986.33
#Mann=4,-1,0
  4792.5    0.07       0  4816.4     0.1       0  4993.1    0.05       0
  5009.0    0.07       0
Bank Sta=4993.1,5009
Exp/Cntr=0.3,0.1

Type RM Length L Ch R = 1,2286,404,404,404
BEGIN DESCRIPTION:
Stream0190 5.0
END DESCRIPTION:
XS GIS Cut Line= 3
      1826075.04     13943224.99      1825875.00     13943275.00
      1825625.04     13943324.99
#Sta/Elev= 30
  4783.8 1997.16  4807.0 1995.06  4814.8 1993.45  4835.4 1992.19  4848.3 1990.75
  4866.3 1987.38  4907.5 1980.94  4930.7 1978.59  4938.5 1976.00  4948.8 1974.38
  4959.1 1971.93  4972.0 1958.75  4979.5 1955.28  4980.0 1954.78  4994.9 1954.78
  4995.4 1955.28  5010.4 1955.69  5020.6 1958.67  5030.8 1960.00  5041.0 1960.98
  5057.0 1961.41  5102.2 1962.99  5112.4 1964.54  5122.6 1967.88  5132.8 1970.42
  5150.5 1973.62  5183.8 1980.67  5204.2 1983.09  5214.4 1985.04  5244.9 1987.31
#Mann=5,-1,0
  4783.8     0.1       0  4979.5    0.05       0  4995.4     0.1       0
  5057.0    0.07       0  5150.5     0.1       0
Bank Sta=4979.5,4995.4
Exp/Cntr=0.3,0.1

Type RM Length L Ch R = 1,1882,449,449,449
BEGIN DESCRIPTION:
Stream0190 4.0
END DESCRIPTION:
XS GIS Cut Line= 3
      1826034.02     13942882.19      1825625.00     13942975.00
      1825424.97     13943025.01
#Sta/Elev= 30
  4585.2 1996.43  4645.7 1993.33  4663.4 1990.89  4668.5 1991.03  4711.6 1986.37
  4717.5 1985.24  4727.4 1984.68  4754.7 1981.33  4830.3 1974.92  4846.1 1972.59
  4871.3 1970.23  4881.6 1968.24  4889.2 1967.81  4922.6 1963.21  4943.1 1957.71
  4963.6 1957.25  4983.4 1955.37  5004.6 1954.62  5006.9 1953.96  5007.4 1953.46
  5022.4 1953.46  5022.9 1953.96  5035.5 1959.49  5045.8 1966.89  5056.2 1972.42
  5063.9 1975.21  5080.7 1976.12  5105.1 1978.27  5159.2 1984.99  5210.8 1988.32
#Mann=6,-1,0
  4585.2    0.07       0  4727.4     0.1       0  4983.4    0.07       0
  5006.9    0.05       0  5022.9    0.07       0  5080.7     0.1       0
Bank Sta=5006.9,5022.9
Exp/Cntr=0.3,0.1