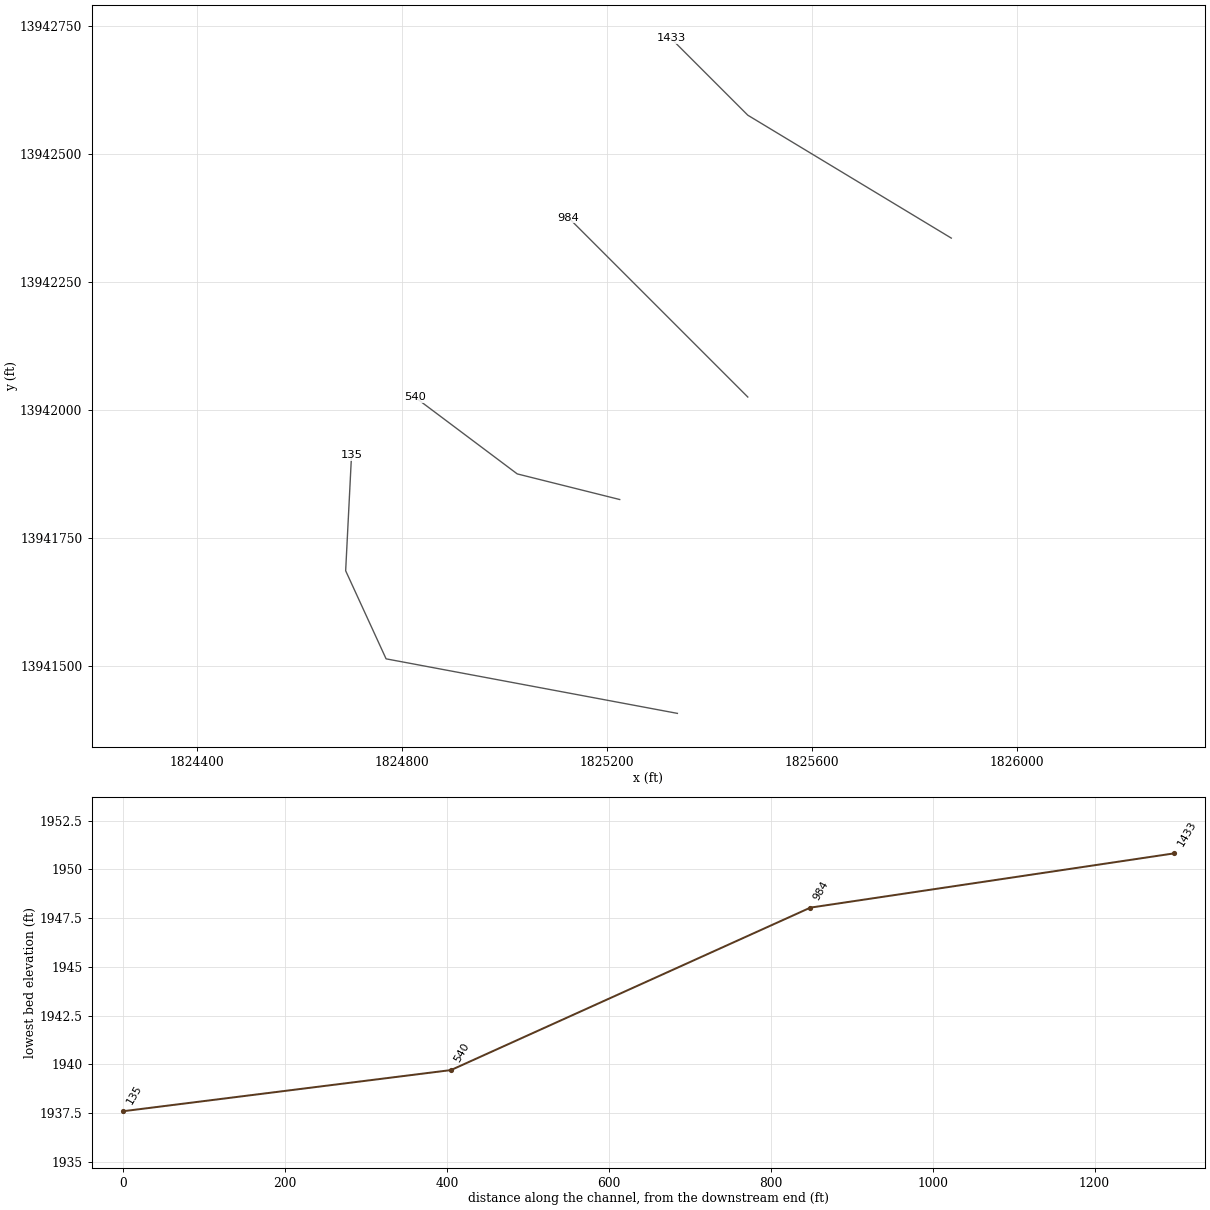
HEC-RAS study Stream0190.prj: Stream0190 Base Level Engineering

--- Stream0190.g01 (geometry) --- (continued)

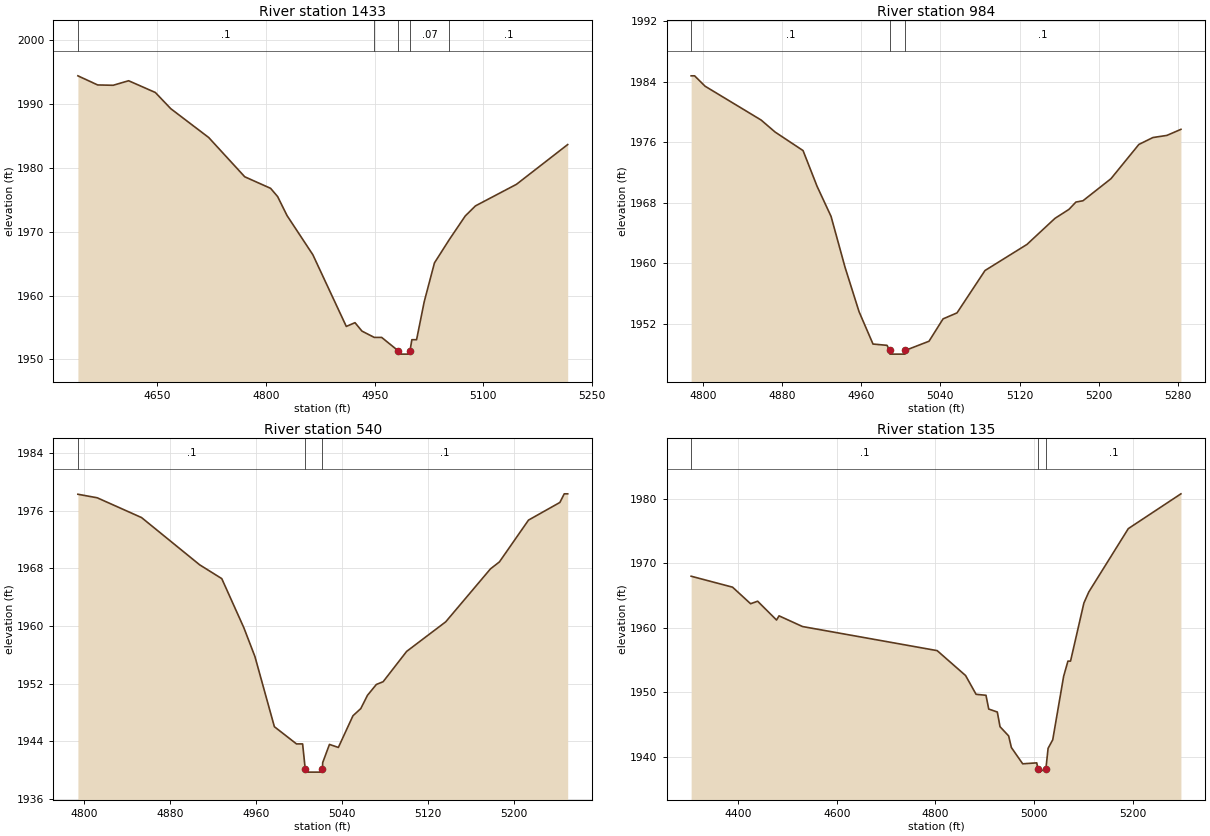
Type RM Length L Ch R = 1,1433,449,449,449
BEGIN DESCRIPTION:
Stream0190 3.0
END DESCRIPTION:
XS GIS Cut Line= 3
      1825872.14     13942335.14      1825475.00     13942575.00
      1825324.99     13942725.01
#Sta/Elev= 30
  4540.3 1994.43  4567.6 1993.00  4589.0 1992.95  4610.3 1993.66  4647.2 1991.82
  4668.5 1989.28  4720.9 1984.76  4770.6 1978.61  4806.3 1976.80  4816.0 1975.51
  4829.0 1972.53  4864.6 1966.40  4910.8 1955.16  4922.8 1955.75  4932.4 1954.43
  4949.4 1953.44  4959.6 1953.44  4982.7 1951.32  4983.2 1950.82  4998.2 1950.82
  4998.7 1951.32  5001.3 1953.08  5007.8 1953.08  5018.4 1959.06  5032.5 1965.12
  5052.8 1968.74  5075.0 1972.47  5089.1 1974.05  5145.7 1977.43  5216.4 1983.66
#Mann=5,-1,0
  4540.3     0.1       0  4949.4    0.07       0  4982.7    0.05       0
  4998.7    0.07       0  5052.8     0.1       0
Bank Sta=4982.7,4998.7
Exp/Cntr=0.3,0.1

Type RM Length L Ch R = 1,984,444,444,444
BEGIN DESCRIPTION:
Stream0190 2.0
END DESCRIPTION:
XS GIS Cut Line= 3
      1825475.00     13942025.00      1825325.00     13942175.00
      1825124.98     13942375.02
#Sta/Elev= 30
  4788.1 1984.75  4791.6 1984.75  4802.2 1983.38  4858.8 1978.92  4873.0 1977.33
  4901.2 1974.89  4915.4 1970.17  4929.5 1966.21  4943.7 1959.47  4957.8 1953.64
  4971.9 1949.37  4986.1 1949.20  4988.6 1948.54  4989.1 1948.04  5004.2 1948.04
  5004.7 1948.54  5028.5 1949.74  5042.7 1952.69  5056.8 1953.48  5085.1 1959.07
  5127.5 1962.51  5155.8 1965.95  5169.9 1967.13  5177.0 1968.10  5184.1 1968.27
  5212.4 1971.18  5240.6 1975.70  5254.8 1976.61  5268.9 1976.89  5283.1 1977.69
#Mann=3,-1,0
  4788.1     0.1       0  4988.6    0.05       0  5004.7     0.1       0
Bank Sta=4988.6,5004.7
Exp/Cntr=0.3,0.1

Type RM Length L Ch R = 1,540,405,405,405
BEGIN DESCRIPTION:
Stream0190 1.0
END DESCRIPTION:
XS GIS Cut Line= 3
      1825225.01     13941825.00      1825025.00     13941875.00
      1824824.97     13942025.02
#Sta/Elev= 30
  4794.1 1978.31  4812.1 1977.82  4853.4 1975.07  4907.5 1968.51  4928.1 1966.59
  4948.7 1959.76  4959.0 1955.76  4977.1 1946.02  4997.7 1943.63  5003.4 1943.63
  5005.8 1940.21  5006.3 1939.71  5021.4 1939.71  5021.9 1940.21  5022.1 1941.03
  5028.4 1943.56  5036.7 1943.14  5050.3 1947.54  5057.6 1948.54  5063.8 1950.38
  5072.1 1951.89  5078.4 1952.27  5100.3 1956.48  5136.7 1960.59  5178.4 1967.95
  5186.7 1968.91  5213.8 1974.72  5243.0 1977.17  5247.1 1978.37  5250.3 1978.37
#Mann=3,-1,0
  4794.1     0.1       0  5005.8    0.05       0  5021.9     0.1       0
Bank Sta=5005.8,5021.9
Exp/Cntr=0.3,0.1

Type RM Length L Ch R = 1,135,0,0,0
BEGIN DESCRIPTION:
Stream0190 0.0
END DESCRIPTION:
XS GIS Cut Line= 4
      1825337.60     13941407.64      1824769.11     13941514.06
      1824690.19     13941685.97      1824701.65     13941911.55
#Sta/Elev= 30
  4304.7 1968.01  4388.7 1966.31  4425.3 1963.74  4439.6 1964.13  4477.9 1961.21
  4483.0 1961.86  4530.5 1960.20  4803.7 1956.46  4861.4 1952.59  4882.6 1949.68
  4902.7 1949.53  4908.3 1947.39  4925.7 1946.93  4931.2 1944.65  4948.7 1943.22
  4954.2 1941.42  4977.2 1938.89  5005.7 1939.04  5008.1 1938.10  5008.6 1937.60
  5024.2 1938.10  5028.7 1941.30  5038.1 1942.62  5060.2 1952.47  5068.9 1954.83
  5074.2 1954.83  5101.3 1963.85  5111.3 1965.57  5191.4 1975.40  5298.1 1980.80
#Mann=3,-1,0
  4304.7     0.1       0  5008.1    0.05       0  5024.2     0.1       0
Bank Sta=5008.1,5024.2
Exp/Cntr=0.3,0.1

Chan Stop Cuts=-1