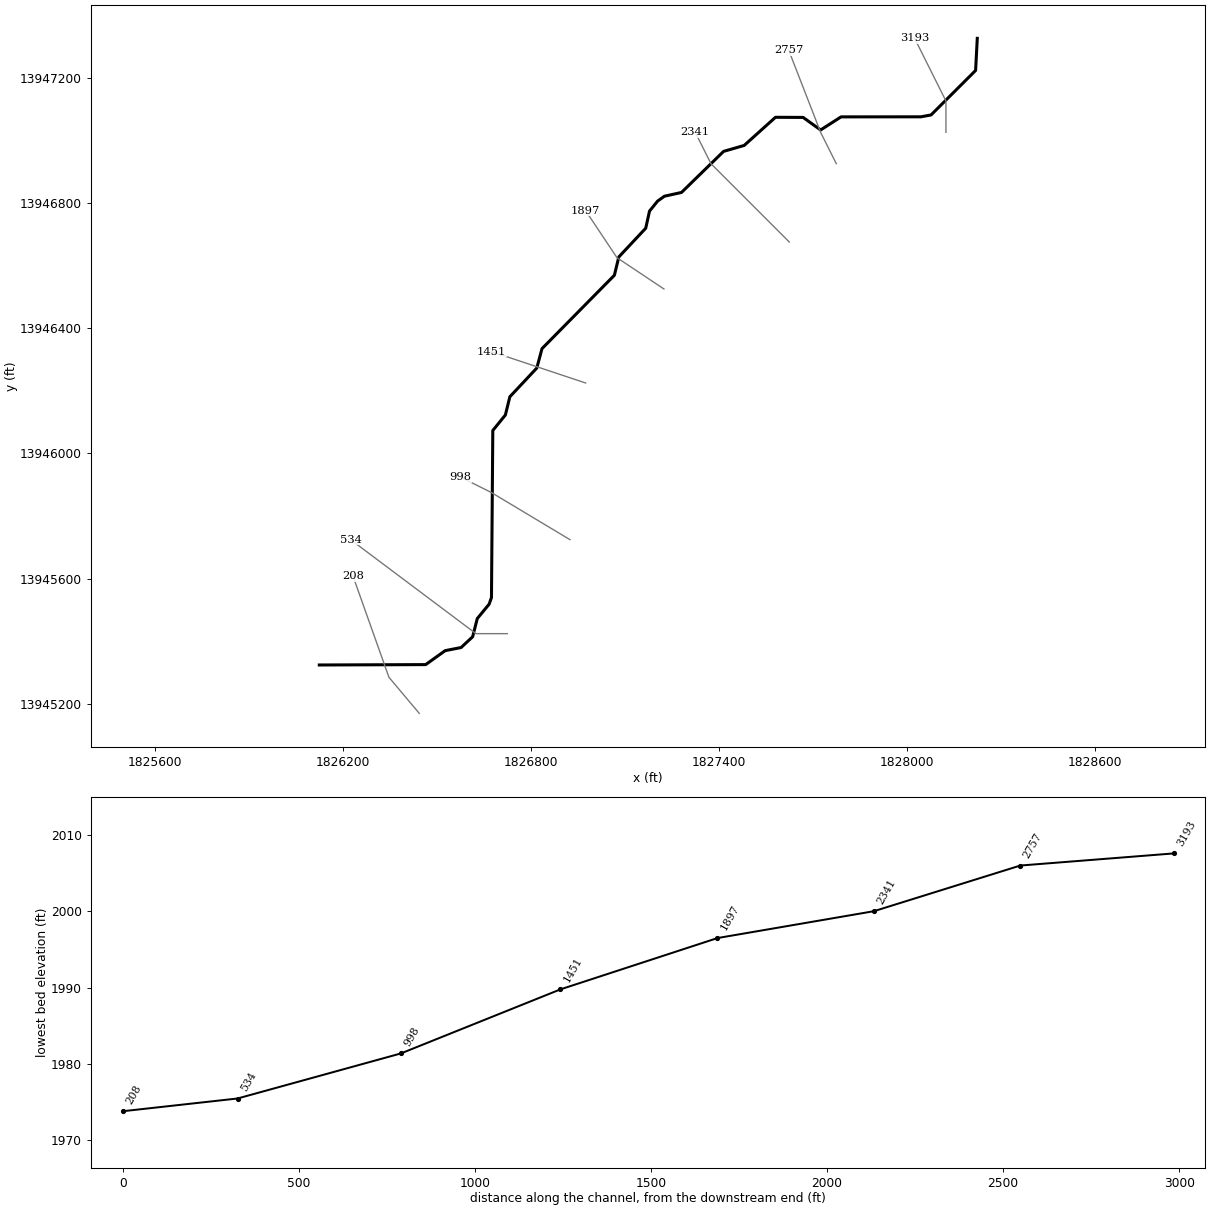
--- Stream0191.prj (project) ---

Proj Title=Stream0191 Base Level Engineering
Current Plan=p01
Default Exp/Contr=0.3,0.1
English Units
Geom File=g01
Flow File=f01
Plan File=p01
BEGIN DESCRIPTION:
Stream0191
END DESCRIPTION:

--- Stream0191.p01 (plan) ---

Plan Title=Multiple Run
Short Identifier=Multiple
Geom File=g01
Flow File=f01
Subcritical Flow
K Sum by GR= 0
Std Step Tol= 0.01
Critical Tol= 0.01
Num of Std Step Trials= 20
Max Error Tol= 0.3
Flow Tol Ratio= 0.001
Split Flow NTrial= 30
Split Flow Tol= 0.02
Split Flow Ratio= 0.02
Log Output Level= 0
Friction Slope Method= 1
Unsteady Friction Slope Method= 2
Unsteady Bridges Friction Slope Method= 1
Parabolic Critical Depth
Global Vel Dist=  1 , 1 , 1
Global Log Level= 0
CheckData=True
Encroach Param= -1, 0, 0, 0
BEGIN DESCRIPTION:
Multiple Run
END DESCRIPTION:

--- Stream0191.f01 (steady flow) ---

Flow Title=Multiple
Number of Profiles=7
Profile Names=10-year,25-year,50-year,1pct_min,100-year,1pct_plu,500-year
River Rch & RM= Stream0191,Reach-1,3193
    1613    2827    4010    2746    5480   10933   10117
Boundary for River Rch & Prof#=Stream0191,Reach-1,1
Up Type=0
Dn Type=3
Dn Slope=0.005
Boundary for River Rch & Prof#=Stream0191,Reach-1,2
Up Type=0
Dn Type=3
Dn Slope=0.005
Boundary for River Rch & Prof#=Stream0191,Reach-1,3
Up Type=0
Dn Type=3
Dn Slope=0.005
Boundary for River Rch & Prof#=Stream0191,Reach-1,4
Up Type=0
Dn Type=3
Dn Slope=0.005
Boundary for River Rch & Prof#=Stream0191,Reach-1,5
Up Type=0
Dn Type=3
Dn Slope=0.005
Boundary for River Rch & Prof#=Stream0191,Reach-1,6
Up Type=0
Dn Type=3
Dn Slope=0.005
Boundary for River Rch & Prof#=Stream0191,Reach-1,7
Up Type=0
Dn Type=3
Dn Slope=0.005

--- Stream0191.g01 (geometry) ---

Geom Title=Existing Conditions

River Reach=Stream0191,Reach-1
Reach XY= 30
      1828225.00     13947325.00      1828219.65     13947222.50
      1828077.45     13947080.46      1828045.18     13947074.57
      1827790.16     13947074.34      1827725.00     13947032.56
      1827669.10     13947072.64      1827580.90     13947073.02
      1827481.04     13946983.18      1827415.32     13946964.22
      1827281.03     13946833.17      1827226.43     13946821.11
      1827204.53     13946805.37      1827178.89     13946773.57
      1827166.82     13946718.98      1827080.87     13946627.28
      1827066.84     13946568.95      1826835.78     13946334.68
      1826819.13     13946272.72      1826733.16     13946181.05
      1826718.86     13946122.83      1826678.75     13946073.45
      1826674.49     13945540.21      1826666.91     13945518.92
      1826629.23     13945473.22      1826614.37     13945415.00
      1826577.55     13945380.73      1826526.78     13945370.77
      1826464.50     13945326.20      1826125.00     13945325.00

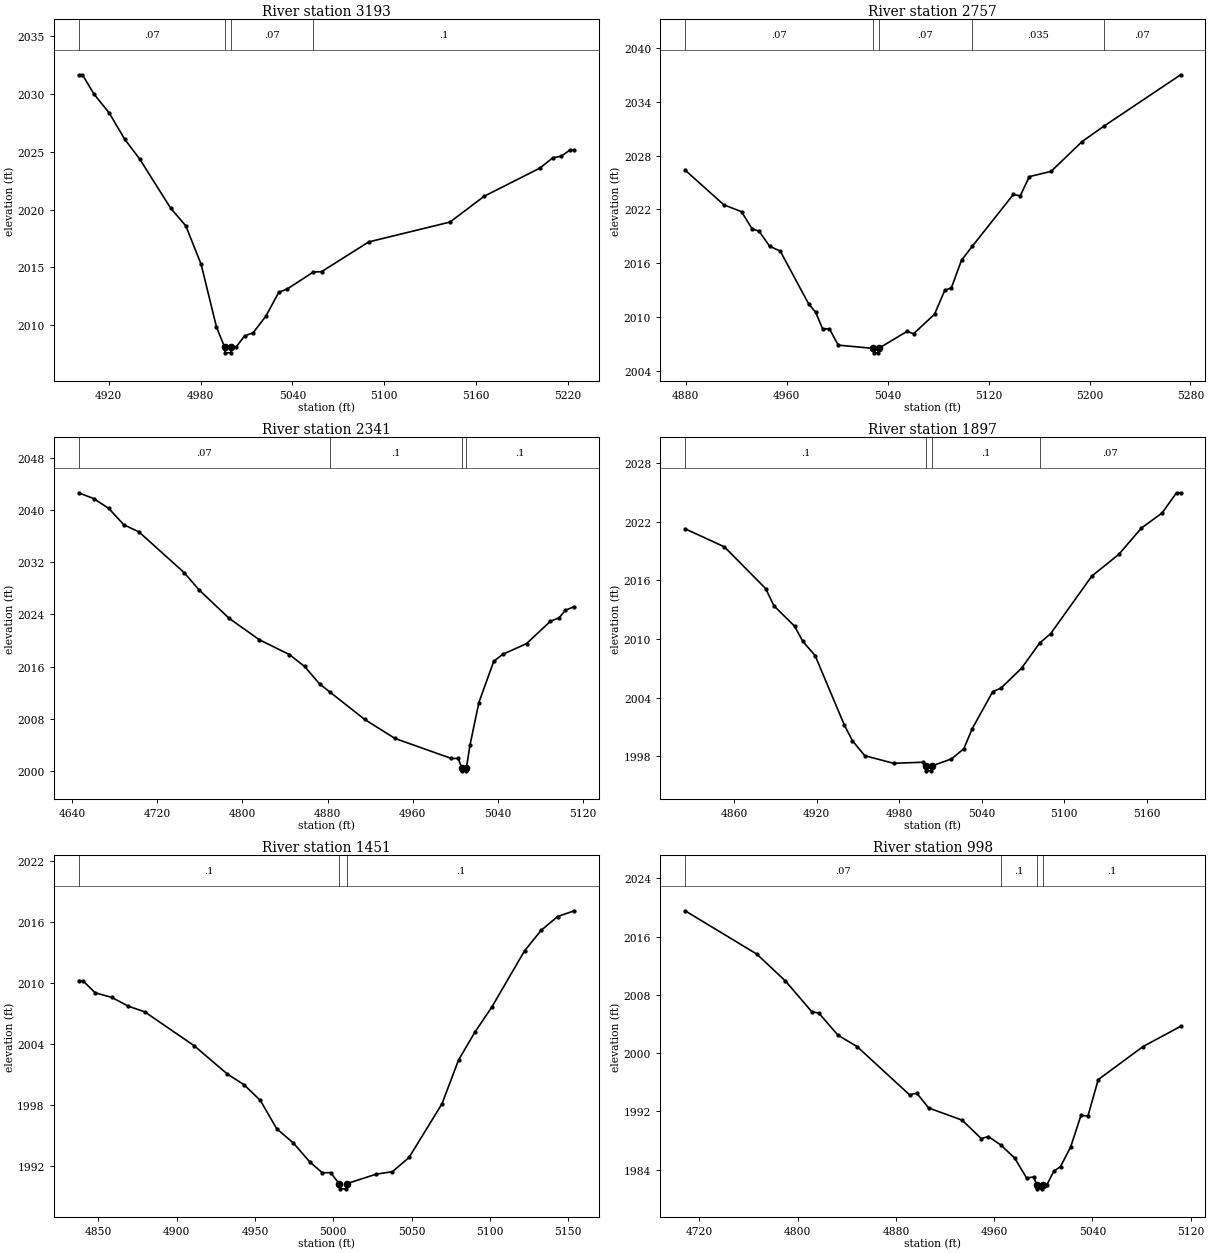
Type RM Length L Ch R = 1,3193,436,436,436
BEGIN DESCRIPTION:
Stream0191 7.0
END DESCRIPTION:
XS GIS Cut Line= 3
      1828125.00     13947025.03      1828125.00     13947125.00
      1828024.99     13947325.02
#Sta/Elev= 30
  4900.4 2031.67  4902.9 2031.67  4910.4 2030.00  4920.4 2028.36  4930.4 2026.11
  4940.4 2024.35  4960.4 2020.14  4970.4 2018.59  4980.4 2015.26  4990.4 2009.84
  4995.7 2008.10  4996.0 2007.60  4999.7 2007.60  5000.0 2008.10  5003.2 2008.10
  5008.8 2009.07  5014.3 2009.33  5022.7 2010.78  5031.1 2012.84  5036.7 2013.13
  5053.6 2014.59  5059.1 2014.63  5089.8 2017.20  5142.9 2018.92  5165.3 2021.16
  5201.6 2023.59  5210.0 2024.48  5215.6 2024.63  5221.2 2025.15  5224.0 2025.15
#Mann=4,-1,0
  4900.4    0.07       0  4995.7    0.05       0  5000.0    0.07       0
  5053.6     0.1       0
Bank Sta=4995.7,5000
Exp/Cntr=0.3,0.1

Type RM Length L Ch R = 1,2757,416,416,416
BEGIN DESCRIPTION:
Stream0191 6.0
END DESCRIPTION:
XS GIS Cut Line= 3
      1827774.98     13946925.04      1827725.00     13947025.00
      1827623.28     13947286.78
#Sta/Elev= 30
  4879.6 2026.39  4910.3 2022.52  4924.3 2021.75  4932.7 2019.83  4938.2 2019.58
  4946.6 2017.89  4955.0 2017.36  4977.4 2011.49  4983.0 2010.54  4988.6 2008.68
  4994.0 2008.68  5000.9 2006.87  5028.6 2006.51  5028.9 2006.01  5032.7 2006.01
  5033.0 2006.51  5055.4 2008.40  5060.7 2008.15  5077.2 2010.31  5085.3 2012.97
  5090.6 2013.27  5098.6 2016.34  5107.0 2017.87  5139.7 2023.68  5145.1 2023.51
  5152.3 2025.66  5169.6 2026.25  5194.1 2029.57  5211.2 2031.27  5272.2 2037.02
#Mann=5,-1,0
  4879.6    0.07       0  5028.6    0.05       0  5033.0    0.07       0
  5107.0   0.035       0  5211.2    0.07       0
Bank Sta=5028.6,5033
Exp/Cntr=0.3,0.1

Type RM Length L Ch R = 1,2341,444,444,444
BEGIN DESCRIPTION:
Stream0191 5.0
END DESCRIPTION:
XS GIS Cut Line= 3
      1827625.02     13946674.98      1827375.00     13946925.00
      1827324.99     13947025.01
#Sta/Elev= 30
  4646.2 2042.63  4660.4 2041.74  4674.5 2040.23  4688.7 2037.72  4702.8 2036.64
  4745.2 2030.41  4759.4 2027.74  4787.6 2023.38  4815.9 2020.11  4844.2 2017.83
  4858.4 2016.02  4872.5 2013.34  4881.9 2012.13  4914.9 2007.89  4943.2 2004.99
  4996.2 2001.92  5002.6 2001.92  5006.0 2000.52  5006.3 2000.02  5010.1 2000.02
  5010.4 2000.52  5013.8 2003.99  5022.1 2010.49  5036.1 2016.82  5044.5 2017.87
  5066.9 2019.52  5089.2 2022.93  5097.6 2023.48  5103.2 2024.62  5111.6 2025.18
#Mann=4,-1,0
  4646.2    0.07       0  4881.9     0.1       0  5006.0    0.05       0
  5010.4     0.1       0
Bank Sta=5006,5010.4
Exp/Cntr=0.3,0.1

Type RM Length L Ch R = 1,1897,446,446,446
BEGIN DESCRIPTION:
Stream0191 4.0
END DESCRIPTION:
XS GIS Cut Line= 3
      1827224.99     13946525.01      1827075.00     13946625.00
      1826975.02     13946774.96
#Sta/Elev= 30
  4824.2 2021.29  4852.7 2019.45  4882.8 2015.17  4888.8 2013.41  4903.8 2011.32
  4909.8 2009.77  4918.8 2008.30  4939.9 2001.24  4945.9 1999.59  4954.9 1998.05
  4975.9 1997.27  4997.0 1997.38  4999.3 1997.00  4999.6 1996.50  5003.4 1996.50
  5003.7 1997.00  5018.0 1997.72  5027.0 1998.77  5033.0 2000.80  5048.0 2004.61
  5054.0 2004.97  5069.1 2007.03  5082.1 2009.59  5090.1 2010.54  5120.1 2016.45
  5139.7 2018.67  5156.2 2021.37  5171.2 2022.91  5181.7 2024.98  5184.7 2024.98
#Mann=4,-1,0
  4824.2     0.1       0  4999.3    0.05       0  5003.7     0.1       0
  5082.1    0.07       0
Bank Sta=4999.3,5003.7
Exp/Cntr=0.3,0.1

Type RM Length L Ch R = 1,1451,453,453,453
BEGIN DESCRIPTION:
Stream0191 3.0
END DESCRIPTION:
XS GIS Cut Line= 3
      1826975.04     13946224.99      1826825.00     13946275.00
      1826674.97     13946325.01
#Sta/Elev= 30
  4837.5 2010.26  4840.2 2010.26  4848.1 2009.06  4858.6 2008.62  4869.2 2007.75
  4879.7 2007.19  4911.3 2003.85  4932.4 2001.07  4943.0 2000.03  4953.5 1998.47
  4964.0 1995.67  4974.6 1994.28  4985.1 1992.41  4993.0 1991.36  4998.3 1991.36
  5003.9 1990.27  5004.2 1989.77  5008.2 1989.77  5008.5 1990.27  5027.3 1991.21
  5037.8 1991.46  5048.4 1992.86  5069.4 1998.13  5080.0 2002.45  5090.5 2005.21
  5101.1 2007.63  5122.1 2013.19  5132.7 2015.21  5143.2 2016.57  5153.8 2017.14
#Mann=3,-1,0
  4837.5     0.1       0  5003.9    0.05       0  5008.5     0.1       0
Bank Sta=5003.9,5008.5
Exp/Cntr=0.3,0.1

Type RM Length L Ch R = 1,998,464,464,464
BEGIN DESCRIPTION:
Stream0191 2.0
END DESCRIPTION:
XS GIS Cut Line= 3
      1826925.04     13945724.98      1826675.00     13945875.00
      1826574.99     13945925.00
#Sta/Elev= 30
  4708.4 2019.54  4766.8 2013.59  4790.1 2009.90  4811.5 2005.69  4817.3 2005.49
  4832.8 2002.47  4848.4 2000.90  4891.1 1994.28  4897.0 1994.50  4906.7 1992.47
  4933.9 1990.80  4949.5 1988.27  4955.3 1988.55  4965.2 1987.41  4976.7 1985.60
  4986.4 1982.86  4992.2 1983.00  4994.7 1981.87  4995.1 1981.37  4999.1 1981.37
  4999.4 1981.87  5002.8 1981.87  5008.4 1983.76  5014.0 1984.43  5022.3 1987.13
  5030.7 1991.48  5036.3 1991.35  5044.7 1996.36  5081.0 2000.88  5111.8 2003.68
#Mann=4,-1,0
  4708.4    0.07       0  4965.2     0.1       0  4994.7    0.05       0
  4999.4     0.1       0
Bank Sta=4994.7,4999.4
Exp/Cntr=0.3,0.1

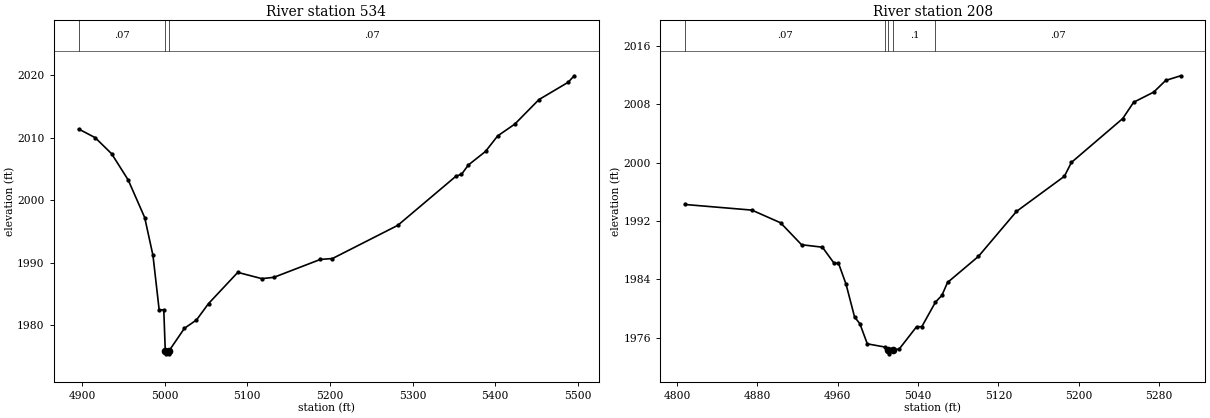
Type RM Length L Ch R = 1,534,326,326,326
BEGIN DESCRIPTION:
Stream0191 1.0
END DESCRIPTION:
XS GIS Cut Line= 3
      1826724.96     13945425.00      1826625.00     13945425.00
      1826224.97     13945725.02
#Sta/Elev= 30
  4895.7 2011.37  4915.7 2009.99  4935.7 2007.41  4955.7 2003.23  4975.7 1997.22
  4985.7 1991.18  4993.2 1982.49  4998.8 1982.49  5000.6 1975.96  5000.9 1975.46
  5005.0 1975.46  5005.3 1975.96  5023.8 1979.54  5038.4 1980.87  5053.0 1983.49
  5088.4 1988.47  5117.5 1987.47  5132.1 1987.68  5188.4 1990.54  5203.0 1990.68
  5282.1 1995.98  5353.0 2003.88  5359.2 2004.11  5367.5 2005.61  5388.4 2007.79
  5403.0 2010.26  5423.8 2012.15  5453.0 2016.06  5488.4 2018.83  5495.7 2019.87
#Mann=3,-1,0
  4895.7    0.07       0  5000.6    0.05       0  5005.3    0.07       0
Bank Sta=5000.6,5005.3
Exp/Cntr=0.3,0.1

Type RM Length L Ch R = 1,208,0,0,0
BEGIN DESCRIPTION:
Stream0191 0.0
END DESCRIPTION:
XS GIS Cut Line= 3
      1826444.05     13945170.56      1826347.19     13945285.82
      1826232.36     13945609.08
#Sta/Elev= 30
  4807.9 1994.28  4874.4 1993.51  4903.0 1991.77  4923.9 1988.76  4944.7 1988.42
  4956.3 1986.22  4960.7 1986.22  4968.2 1983.35  4976.7 1978.85  4982.0 1977.92
  4989.4 1975.16  5006.7 1974.73  5010.5 1974.29  5010.8 1973.79  5015.3 1974.29
  5021.3 1974.47  5038.4 1977.50  5043.7 1977.52  5057.3 1980.89  5063.7 1981.81
  5069.3 1983.58  5100.1 1987.16  5138.0 1993.33  5185.7 1998.15  5192.7 2000.05
  5243.8 2006.07  5254.7 2008.31  5274.7 2009.70  5286.6 2011.30  5301.5 2011.94
#Mann=5,-1,0
  4807.9    0.07       0  5006.7     0.1       0  5010.5    0.05       0
  5015.3     0.1       0  5057.3    0.07       0
Bank Sta=5010.5,5015.3
Exp/Cntr=0.3,0.1

Chan Stop Cuts=-1