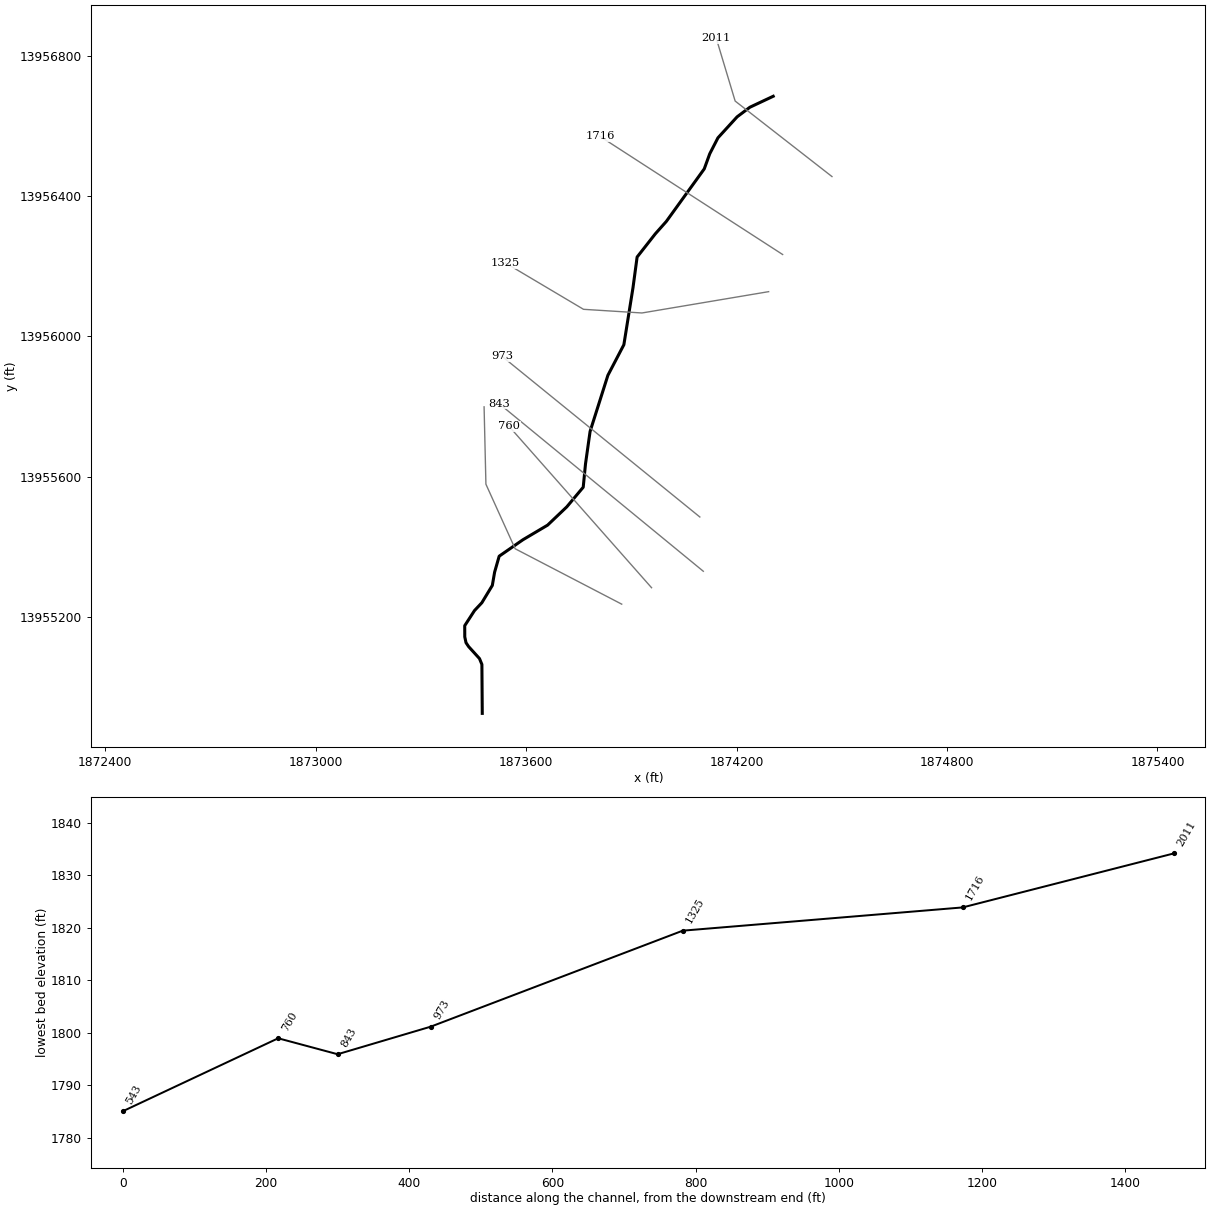
--- Stream0192.prj (project) ---

Proj Title=Stream0192 Base Level Engineering
Current Plan=p01
Default Exp/Contr=0.3,0.1
English Units
Geom File=g01
Flow File=f01
Plan File=p01
BEGIN DESCRIPTION:
Stream0192
END DESCRIPTION:

--- Stream0192.p01 (plan) ---

Plan Title=Multiple Run
Short Identifier=Multiple
Geom File=g01
Flow File=f01
Subcritical Flow
K Sum by GR= 0
Std Step Tol= 0.01
Critical Tol= 0.01
Num of Std Step Trials= 20
Max Error Tol= 0.3
Flow Tol Ratio= 0.001
Split Flow NTrial= 30
Split Flow Tol= 0.02
Split Flow Ratio= 0.02
Log Output Level= 0
Friction Slope Method= 1
Unsteady Friction Slope Method= 2
Unsteady Bridges Friction Slope Method= 1
Parabolic Critical Depth
Global Vel Dist=  1 , 1 , 1
Global Log Level= 0
CheckData=True
Encroach Param= -1, 0, 0, 0
BEGIN DESCRIPTION:
Multiple Run
END DESCRIPTION:

--- Stream0192.f01 (steady flow) ---

Flow Title=Multiple
Number of Profiles=7
Profile Names=10-year,25-year,50-year,1pct_min,100-year,1pct_plu,500-year
River Rch & RM= Stream0192,Reach-1,2011
    1434    2495    3525    2407    4802    9581    8802
Boundary for River Rch & Prof#=Stream0192,Reach-1,1
Up Type=0
Dn Type=3
Dn Slope=0.005
Boundary for River Rch & Prof#=Stream0192,Reach-1,2
Up Type=0
Dn Type=3
Dn Slope=0.005
Boundary for River Rch & Prof#=Stream0192,Reach-1,3
Up Type=0
Dn Type=3
Dn Slope=0.005
Boundary for River Rch & Prof#=Stream0192,Reach-1,4
Up Type=0
Dn Type=3
Dn Slope=0.005
Boundary for River Rch & Prof#=Stream0192,Reach-1,5
Up Type=0
Dn Type=3
Dn Slope=0.005
Boundary for River Rch & Prof#=Stream0192,Reach-1,6
Up Type=0
Dn Type=3
Dn Slope=0.005
Boundary for River Rch & Prof#=Stream0192,Reach-1,7
Up Type=0
Dn Type=3
Dn Slope=0.005

--- Stream0192.g01 (geometry) ---

Geom Title=Existing Conditions

River Reach=Stream0192,Reach-1
Reach XY= 30
      1874304.47     13956684.31      1874238.07     13956653.06
      1874201.61     13956625.71      1874146.92     13956565.82
      1874123.48     13956520.24      1874107.86     13956477.27
      1873999.79     13956327.54      1873968.54     13956292.38
      1873916.45     13956225.97      1873904.73     13956138.73
      1873878.69     13955975.97      1873833.12     13955888.73
      1873782.34     13955728.58      1873769.32     13955636.13
      1873762.81     13955569.72      1873715.93     13955513.73
      1873661.24     13955461.65      1873590.93     13955419.98
      1873523.22     13955373.11      1873510.20     13955327.54
      1873503.69     13955289.77      1873473.74     13955240.30
      1873452.91     13955218.16      1873425.00     13955175.00
      1873425.12     13955143.20      1873428.64     13955126.51
      1873436.05     13955115.44      1873467.13     13955081.17
      1873473.94     13955064.56      1873475.00     13954925.00

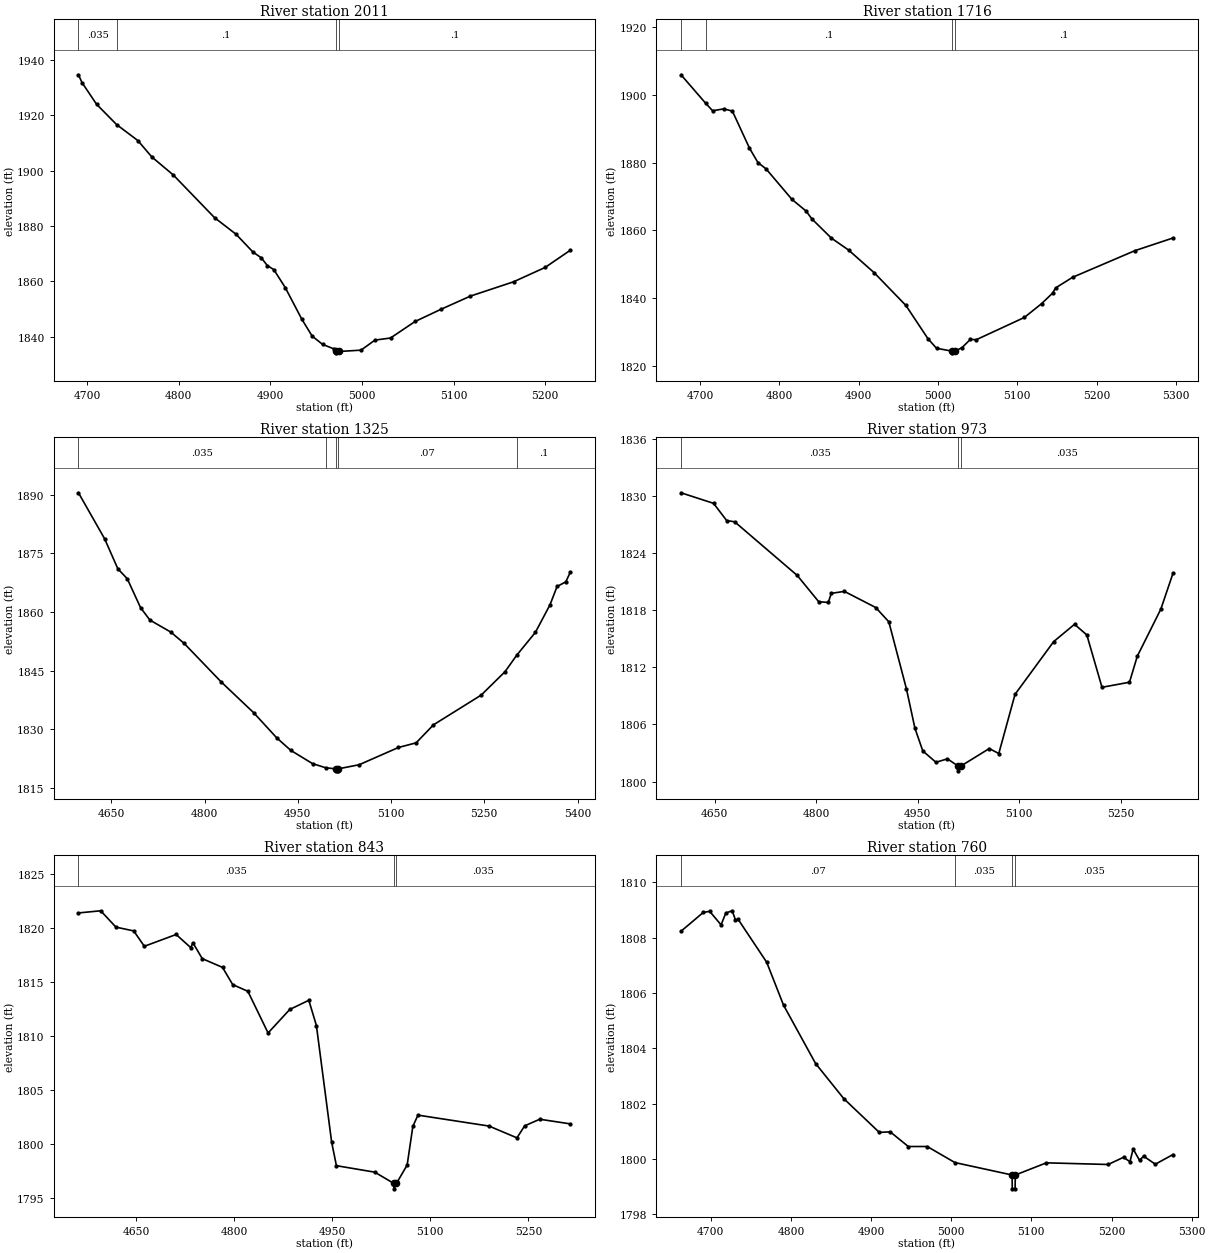
Type RM Length L Ch R = 1,2011,295,295,295
BEGIN DESCRIPTION:
Stream0192 6.0
END DESCRIPTION:
XS GIS Cut Line= 3
      1874472.00     13956455.37      1874195.93     13956670.67
      1874142.12     13956849.45
#Sta/Elev= 30
  4690.7 1934.64  4694.6 1931.81  4710.5 1923.97  4732.3 1916.65  4755.5 1910.87
  4770.7 1904.96  4794.3 1898.39  4839.2 1882.99  4862.6 1877.02  4881.1 1870.57
  4890.1 1868.51  4896.8 1865.69  4903.9 1864.20  4916.3 1857.75  4934.3 1846.36
  4945.7 1840.19  4957.1 1837.19  4970.0 1835.50  4971.4 1834.64  4971.7 1834.14
  4975.4 1834.64  4999.0 1835.11  5014.2 1838.74  5031.2 1839.50  5058.0 1845.47
  5086.2 1849.87  5118.4 1854.65  5165.4 1859.81  5199.8 1864.99  5227.5 1871.25
#Mann=4,-1,0
  4690.7   0.035       0  4732.3     0.1       0  4971.4    0.05       0
  4975.4     0.1       0
Bank Sta=4971.4,4975.4
Exp/Cntr=0.3,0.1

Type RM Length L Ch R = 1,1716,391,391,391
BEGIN DESCRIPTION:
Stream0192 5.0
END DESCRIPTION:
XS GIS Cut Line= 2
      1874331.34     13956233.17      1873810.55     13956569.95
#Sta/Elev= 30
  4676.2 1905.95  4707.3 1897.54  4716.0 1895.34  4730.3 1895.88  4741.0 1895.22
  4762.5 1884.30  4773.2 1880.03  4783.5 1878.15  4816.0 1869.17  4833.9 1865.71
  4841.1 1863.41  4865.8 1857.72  4887.5 1854.19  4919.7 1847.51  4959.7 1837.84
  4987.6 1828.00  4998.3 1825.21  5017.7 1824.35  5018.0 1823.85  5021.7 1824.35
  5030.4 1825.39  5041.1 1827.84  5048.3 1827.71  5109.0 1834.29  5130.7 1838.36
  5144.8 1841.52  5148.3 1843.00  5169.8 1846.15  5248.4 1854.02  5296.4 1857.76
#Mann=4,-1,0
  4676.2   0.035       0  4707.3     0.1       0  5017.7    0.05       0
  5021.7     0.1       0
Bank Sta=5017.7,5021.7
Exp/Cntr=0.3,0.1

Type RM Length L Ch R = 1,1325,352,352,352
BEGIN DESCRIPTION:
Stream0192 4.0
END DESCRIPTION:
XS GIS Cut Line= 4
      1874291.40     13956127.26      1873930.30     13956066.50
      1873763.63     13956076.92      1873541.42     13956208.86
#Sta/Elev= 30
  4597.0 1890.46  4639.1 1878.71  4660.4 1871.04  4675.6 1868.49  4696.9 1861.12
  4712.0 1857.93  4745.6 1854.87  4766.8 1852.02  4826.7 1842.13  4878.8 1834.29
  4915.9 1827.87  4938.7 1824.64  4973.6 1821.27  4994.5 1820.22  5010.7 1819.92
  5010.9 1819.42  5014.4 1819.42  5014.7 1819.92  5048.7 1820.98  5111.9 1825.39
  5140.3 1826.57  5168.2 1831.17  5245.0 1838.77  5283.4 1844.76  5302.1 1848.94
  5332.3 1854.82  5355.8 1861.87  5367.1 1866.52  5381.1 1867.70  5388.6 1870.23
#Mann=5,-1,0
  4597.0   0.035       0  4994.5    0.07       0  5010.7    0.05       0
  5014.7    0.07       0  5302.1     0.1       0
Bank Sta=5010.7,5014.7
Exp/Cntr=0.3,0.1

Type RM Length L Ch R = 1,973,130,130,130
BEGIN DESCRIPTION:
Stream0192 3.0
END DESCRIPTION:
XS GIS Cut Line= 2
      1874095.25     13955484.88      1873530.97     13955943.26
#Sta/Elev= 30
  4600.4 1830.35  4648.5 1829.24  4667.9 1827.43  4679.7 1827.30  4772.2 1821.66
  4803.8 1818.91  4818.0 1818.82  4822.5 1819.78  4841.8 1819.99  4888.2 1818.29
  4907.5 1816.79  4933.5 1809.75  4946.1 1805.60  4957.7 1803.22  4977.1 1802.03
  4994.1 1802.39  5009.9 1801.63  5010.1 1801.13  5013.9 1801.63  5055.9 1803.47
  5070.0 1802.95  5094.0 1809.17  5151.1 1814.71  5181.9 1816.53  5200.1 1815.41
  5222.5 1809.91  5263.1 1810.44  5274.7 1813.18  5309.5 1818.13  5327.4 1821.89
#Mann=3,-1,0
  4600.4   0.035       0  5009.9   0.035       0  5013.9   0.035       0
Bank Sta=5009.9,5013.9
Exp/Cntr=0.3,0.1

Type RM Length L Ch R = 1,843,83,83,83
BEGIN DESCRIPTION:
Stream0192 1.0
END DESCRIPTION:
XS GIS Cut Line= 2
      1874105.19     13955330.12      1873523.64     13955807.51
#Sta/Elev= 30
  4561.9 1821.37  4595.9 1821.57  4619.2 1820.06  4646.4 1819.71  4662.7 1818.29
  4711.3 1819.38  4733.7 1818.16  4736.9 1818.62  4751.2 1817.15  4782.2 1816.34
  4797.8 1814.75  4821.0 1814.13  4851.9 1810.28  4885.0 1812.45  4914.2 1813.30
  4925.8 1810.97  4949.1 1800.20  4956.4 1798.02  5015.1 1797.42  5044.2 1796.38
  5044.4 1795.88  5048.2 1796.38  5064.6 1798.08  5073.3 1801.65  5081.1 1802.69
  5189.8 1801.68  5232.5 1800.59  5244.3 1801.70  5267.4 1802.31  5314.3 1801.88
#Mann=3,-1,0
  4561.9   0.035       0  5044.2   0.035       0  5048.2   0.035       0
Bank Sta=5044.2,5048.2
Exp/Cntr=0.3,0.1

Type RM Length L Ch R = 1,760,217,217,217
BEGIN DESCRIPTION:
Stream0192 2.0
END DESCRIPTION:
XS GIS Cut Line= 2
      1873957.63     13955283.23      1873551.36     13955743.33
#Sta/Elev= 30
  4662.9 1808.23  4690.7 1808.91  4698.7 1808.95  4712.9 1808.46  4718.8 1808.89
  4726.8 1808.97  4730.8 1808.64  4734.2 1808.66  4769.8 1807.11  4790.8 1805.56
  4830.8 1803.45  4866.0 1802.18  4910.3 1800.96  4923.9 1800.98  4946.5 1800.45
  4970.1 1800.45  5004.6 1799.87  5076.0 1799.42  5076.2 1798.92  5079.7 1798.92
  5080.0 1799.42  5118.8 1799.86  5195.8 1799.80  5215.0 1800.06  5223.0 1799.90
  5227.0 1800.36  5235.0 1799.95  5240.0 1800.10  5254.7 1799.81  5276.7 1800.16
#Mann=4,-1,0
  4662.9    0.07       0  5004.6   0.035       0  5076.0    0.05       0
  5080.0   0.035       0
Bank Sta=5076,5080
Exp/Cntr=0.3,0.1

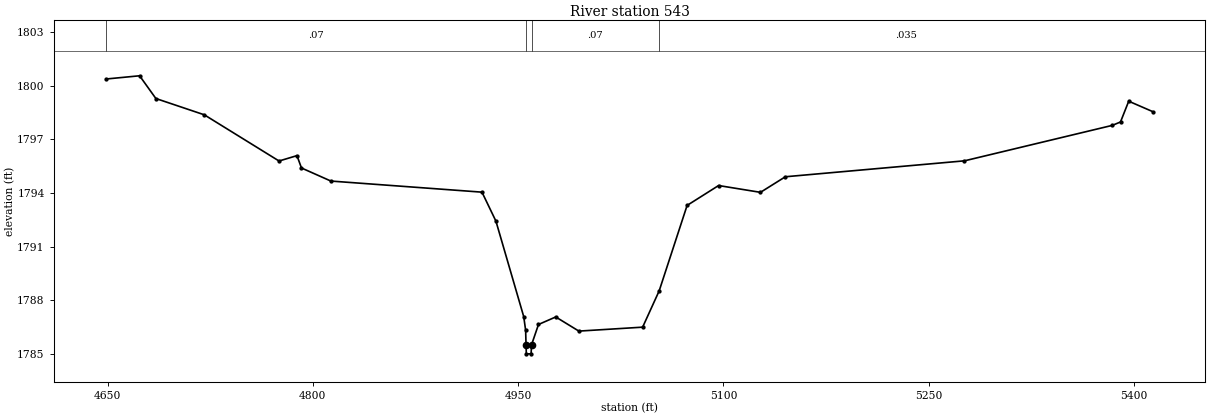
Type RM Length L Ch R = 1,543,0,0,0
BEGIN DESCRIPTION:
Stream0192 0.0
END DESCRIPTION:
XS GIS Cut Line= 4
      1873872.54     13955236.37      1873568.74     13955394.35
      1873485.41     13955578.37      1873480.20     13955798.88
#Sta/Elev= 30
  4649.0 1800.37  4673.4 1800.55  4685.3 1799.28  4720.7 1798.37  4775.3 1795.79
  4788.4 1796.09  4791.7 1795.40  4813.2 1794.67  4923.6 1794.05  4933.8 1792.43
  4954.1 1787.10  4955.5 1786.34  4955.8 1785.52  4956.0 1785.02  4959.5 1785.02
  4959.8 1785.52  4964.9 1786.66  4977.5 1787.08  4994.4 1786.29  5041.0 1786.51
  5053.1 1788.54  5073.5 1793.31  5096.5 1794.42  5127.1 1794.04  5145.3 1794.91
  5276.2 1795.80  5384.2 1797.78  5390.2 1797.97  5396.2 1799.13  5414.0 1798.54
#Mann=4,-1,0
  4649.0    0.07       0  4955.8    0.05       0  4959.8    0.07       0
  5053.1   0.035       0
Bank Sta=4955.8,4959.8
Exp/Cntr=0.3,0.1

Chan Stop Cuts=-1