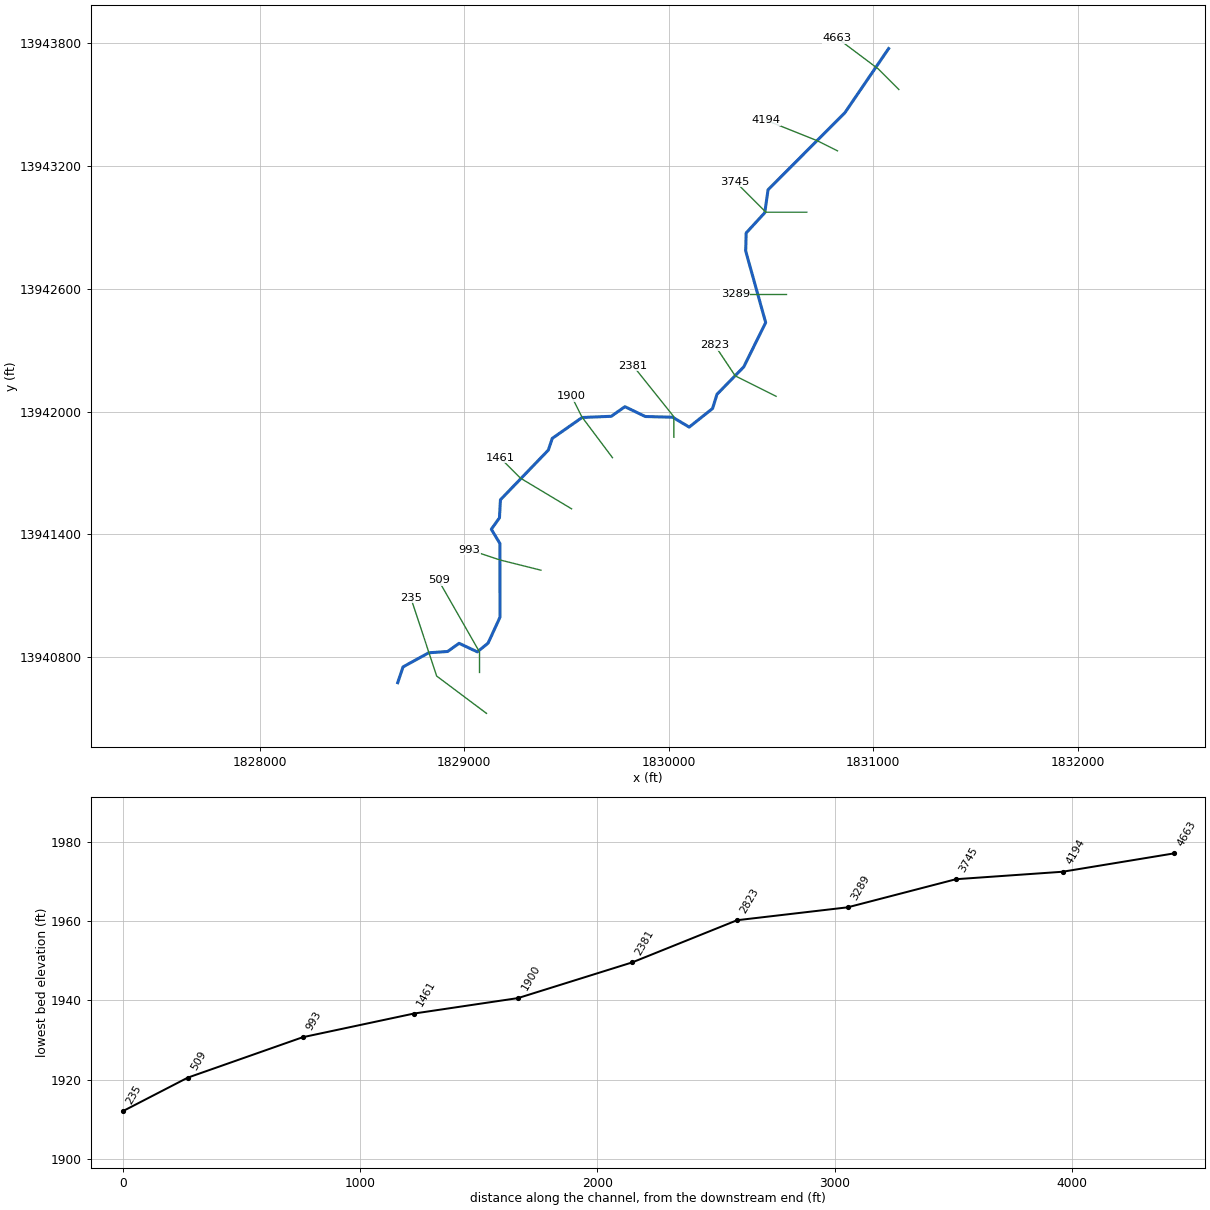
--- Stream0194.prj (project) ---

Proj Title=Stream0194 Base Level Engineering
Current Plan=p01
Default Exp/Contr=0.3,0.1
English Units
Geom File=g01
Flow File=f01
Plan File=p01
BEGIN DESCRIPTION:
Stream0194
END DESCRIPTION:

--- Stream0194.p01 (plan) ---

Plan Title=Multiple Run
Short Identifier=Multiple
Geom File=g01
Flow File=f01
Subcritical Flow
K Sum by GR= 0
Std Step Tol= 0.01
Critical Tol= 0.01
Num of Std Step Trials= 20
Max Error Tol= 0.3
Flow Tol Ratio= 0.001
Split Flow NTrial= 30
Split Flow Tol= 0.02
Split Flow Ratio= 0.02
Log Output Level= 0
Friction Slope Method= 1
Unsteady Friction Slope Method= 2
Unsteady Bridges Friction Slope Method= 1
Parabolic Critical Depth
Global Vel Dist=  1 , 1 , 1
Global Log Level= 0
CheckData=True
Encroach Param= -1, 0, 0, 0
BEGIN DESCRIPTION:
Multiple Run
END DESCRIPTION:

--- Stream0194.f01 (steady flow) ---

Flow Title=Multiple
Number of Profiles=7
Profile Names=10-year,25-year,50-year,1pct_min,100-year,1pct_plu,500-year
River Rch & RM= Stream0194,Reach-1,4663
    2056    3669    5270    3652    7287   14540   13783
Boundary for River Rch & Prof#=Stream0194,Reach-1,1
Up Type=0
Dn Type=3
Dn Slope=0.005
Boundary for River Rch & Prof#=Stream0194,Reach-1,2
Up Type=0
Dn Type=3
Dn Slope=0.005
Boundary for River Rch & Prof#=Stream0194,Reach-1,3
Up Type=0
Dn Type=3
Dn Slope=0.005
Boundary for River Rch & Prof#=Stream0194,Reach-1,4
Up Type=0
Dn Type=3
Dn Slope=0.005
Boundary for River Rch & Prof#=Stream0194,Reach-1,5
Up Type=0
Dn Type=3
Dn Slope=0.005
Boundary for River Rch & Prof#=Stream0194,Reach-1,6
Up Type=0
Dn Type=3
Dn Slope=0.005
Boundary for River Rch & Prof#=Stream0194,Reach-1,7
Up Type=0
Dn Type=3
Dn Slope=0.005

--- Stream0194.g01 (geometry) ---

Geom Title=Existing Conditions

River Reach=Stream0194,Reach-1
Reach XY= 30
      1831075.00     13943775.00      1830861.37     13943461.79
      1830485.52     13943084.79      1830469.46     13942972.58
      1830378.47     13942873.50      1830376.10     13942785.55
      1830473.91     13942435.54      1830366.86     13942218.94
      1830235.78     13942084.68      1830214.23     13942015.30
      1830100.04     13941924.50      1830019.07     13941972.70
      1829885.50     13941976.25      1829785.69     13942024.23
      1829719.07     13941977.30      1829576.47     13941971.45
      1829430.62     13941869.38      1829411.27     13941812.02
      1829177.15     13941569.11      1829172.44     13941480.90
      1829132.56     13941425.00      1829174.82     13941355.02
      1829174.94     13940995.02      1829116.98     13940868.57
      1829064.51     13940825.58      1828975.01     13940867.41
      1828919.11     13940827.55      1828826.58     13940821.18
      1828701.15     13940752.28      1828675.00     13940675.00

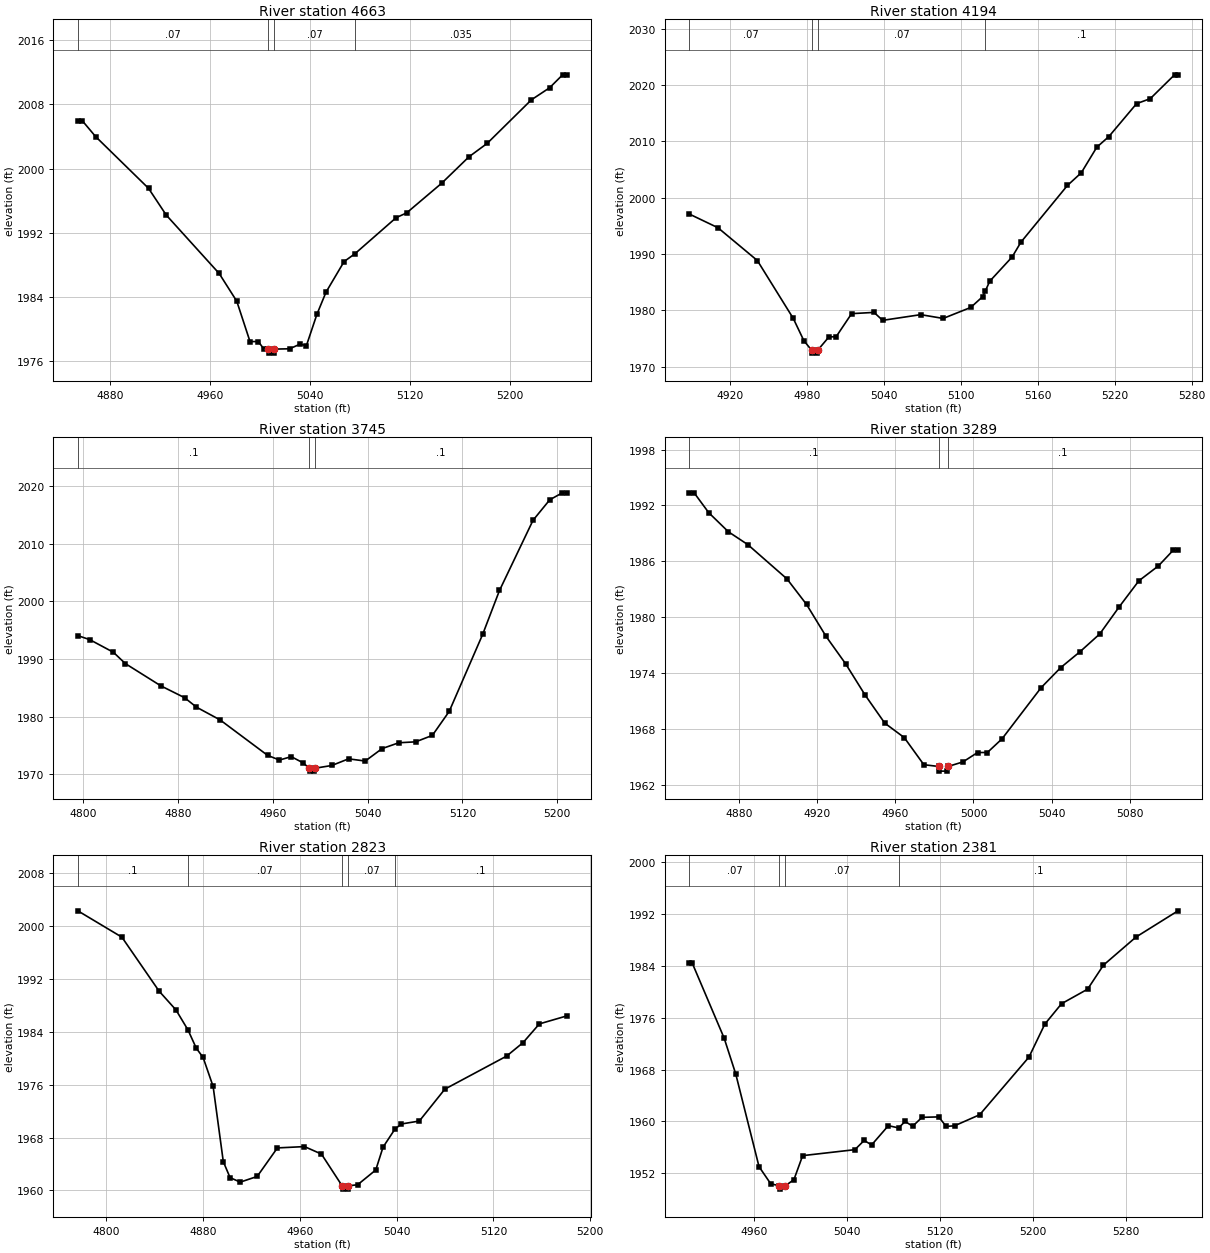
Type RM Length L Ch R = 1,4663,469,469,469
BEGIN DESCRIPTION:
Stream0194 10.0
END DESCRIPTION:
XS GIS Cut Line= 3
      1831125.03     13943574.97      1831025.00     13943675.00
      1830824.97     13943825.02
#Sta/Elev= 30
  4854.2 2005.94  4857.8 2005.94  4868.4 2003.98  4910.8 1997.54  4925.0 1994.21
  4967.4 1986.94  4981.5 1983.49  4992.1 1978.47  4998.8 1978.47  5003.0 1977.58
  5006.9 1977.53  5007.3 1977.03  5011.2 1977.03  5011.5 1977.53  5023.8 1977.57
  5032.1 1978.14  5037.3 1977.97  5045.7 1981.86  5053.0 1984.62  5067.5 1988.43
  5076.1 1989.39  5109.2 1993.89  5117.5 1994.47  5145.7 1998.18  5167.5 2001.46
  5182.1 2003.13  5217.5 2008.55  5232.1 2010.05  5242.5 2011.66  5245.7 2011.66
#Mann=4,-1,0
  4854.2    0.07       0  5006.9    0.05       0  5011.5    0.07       0
  5076.1   0.035       0
Bank Sta=5006.9,5011.5
Exp/Cntr=0.3,0.1

Type RM Length L Ch R = 1,4194,449,449,449
BEGIN DESCRIPTION:
Stream0194 9.0
END DESCRIPTION:
XS GIS Cut Line= 3
      1830825.00     13943275.00      1830725.00     13943325.00
      1830474.97     13943425.01
#Sta/Elev= 30
  4888.2 1997.11  4910.6 1994.67  4941.3 1988.85  4969.3 1978.58  4977.6 1974.61
  4983.7 1972.91  4984.0 1972.41  4988.0 1972.41  4988.3 1972.91  4997.2 1975.31
  5002.7 1975.31  5014.8 1979.42  5032.3 1979.64  5039.0 1978.23  5068.7 1979.24
  5086.2 1978.57  5107.7 1980.52  5117.1 1982.46  5119.0 1983.41  5122.5 1985.17
  5140.0 1989.49  5146.8 1992.10  5183.1 2002.18  5193.9 2004.43  5206.0 2008.97
  5215.4 2010.86  5237.0 2016.70  5247.7 2017.59  5266.6 2021.82  5269.3 2021.82
#Mann=4,-1,0
  4888.2    0.07       0  4983.7    0.05       0  4988.3    0.07       0
  5119.0     0.1       0
Bank Sta=4983.7,4988.3
Exp/Cntr=0.3,0.1

Type RM Length L Ch R = 1,3745,456,456,456
BEGIN DESCRIPTION:
Stream0194 8.0
END DESCRIPTION:
XS GIS Cut Line= 3
      1830675.02     13942975.00      1830475.00     13942975.00
      1830324.97     13943125.03
#Sta/Elev= 30
  4795.6 1994.03  4805.6 1993.34  4825.6 1991.14  4835.6 1989.19  4865.6 1985.32
  4885.6 1983.27  4895.6 1981.63  4915.6 1979.41  4955.6 1973.27  4965.6 1972.45
  4975.6 1973.04  4985.6 1971.96  4990.8 1971.03  4991.1 1970.53  4995.1 1970.53
  4995.5 1971.03  5009.8 1971.51  5023.9 1972.66  5038.0 1972.28  5052.2 1974.44
  5066.3 1975.45  5080.5 1975.61  5094.6 1976.73  5108.8 1980.89  5137.0 1994.24
  5151.2 2001.86  5179.5 2014.04  5193.6 2017.59  5204.2 2018.80  5207.8 2018.80
#Mann=3,-1,0
  4795.6     0.1       0  4990.8    0.05       0  4995.5     0.1       0
Bank Sta=4990.8,4995.5
Exp/Cntr=0.3,0.1

Type RM Length L Ch R = 1,3289,466,466,466
BEGIN DESCRIPTION:
Stream0194 7.0
END DESCRIPTION:
XS GIS Cut Line= 3
      1830574.98     13942575.00      1830425.00     13942575.00
      1830324.98     13942575.00
#Sta/Elev= 30
  4854.6 1993.35  4857.1 1993.35  4864.6 1991.21  4874.6 1989.17  4884.6 1987.78
  4904.6 1984.10  4914.6 1981.36  4924.6 1977.92  4934.6 1974.98  4944.6 1971.61
  4954.6 1968.61  4964.6 1967.05  4974.6 1964.14  4982.2 1963.95  4982.5 1963.45
  4986.6 1963.45  4987.0 1963.95  4994.6 1964.44  5002.1 1965.45  5007.1 1965.45
  5014.6 1966.92  5034.6 1972.42  5044.6 1974.57  5054.6 1976.30  5064.6 1978.19
  5074.6 1981.12  5084.6 1983.90  5094.6 1985.50  5102.1 1987.17  5104.6 1987.17
#Mann=3,-1,0
  4854.6     0.1       0  4982.2    0.05       0  4987.0     0.1       0
Bank Sta=4982.2,4987
Exp/Cntr=0.3,0.1

Type RM Length L Ch R = 1,2823,442,442,442
BEGIN DESCRIPTION:
Stream0194 6.0
END DESCRIPTION:
XS GIS Cut Line= 3
      1830525.03     13942074.98      1830325.00     13942175.00
      1830225.01     13942324.98
#Sta/Elev= 30
  4776.6 2002.34  4813.0 1998.35  4843.7 1990.19  4857.7 1987.33  4867.6 1984.31
  4874.5 1981.53  4880.1 1980.14  4888.4 1975.74  4896.8 1964.36  4902.4 1961.94
  4910.8 1961.26  4924.8 1962.12  4941.5 1966.44  4963.9 1966.64  4977.9 1965.51
  4995.0 1960.70  4995.4 1960.20  4999.5 1960.20  4999.8 1960.70  5007.8 1960.86
  5022.8 1963.10  5028.8 1966.55  5038.5 1969.25  5043.8 1970.06  5058.8 1970.51
  5079.9 1975.34  5130.9 1980.34  5144.5 1982.38  5158.0 1985.22  5180.5 1986.42
#Mann=5,-1,0
  4776.6     0.1       0  4867.6    0.07       0  4995.0    0.05       0
  4999.8    0.07       0  5038.5     0.1       0
Bank Sta=4995,4999.8
Exp/Cntr=0.3,0.1

Type RM Length L Ch R = 1,2381,481,481,481
BEGIN DESCRIPTION:
Stream0194 5.0
END DESCRIPTION:
XS GIS Cut Line= 3
      1830025.00     13941874.99      1830025.00     13941975.00
      1829824.98     13942225.03
#Sta/Elev= 30
  4904.6 1984.43  4907.1 1984.43  4934.6 1972.84  4944.6 1967.30  4964.6 1953.03
  4974.6 1950.41  4982.1 1950.07  4982.5 1949.57  4987.1 1950.07  4994.6 1951.03
  5002.1 1954.73  5047.0 1955.65  5055.0 1957.07  5061.4 1956.38  5075.8 1959.35
  5084.6 1959.00  5090.2 1960.00  5096.7 1959.26  5104.7 1960.63  5119.1 1960.70
  5125.5 1959.23  5132.7 1959.33  5154.3 1961.03  5196.7 1969.92  5210.3 1974.99
  5224.7 1978.14  5247.1 1980.38  5260.7 1984.08  5288.7 1988.41  5324.8 1992.45
#Mann=4,-1,0
  4904.6    0.07       0  4982.1    0.05       0  4987.1    0.07       0
  5084.6     0.1       0
Bank Sta=4982.1,4987.1
Exp/Cntr=0.3,0.1

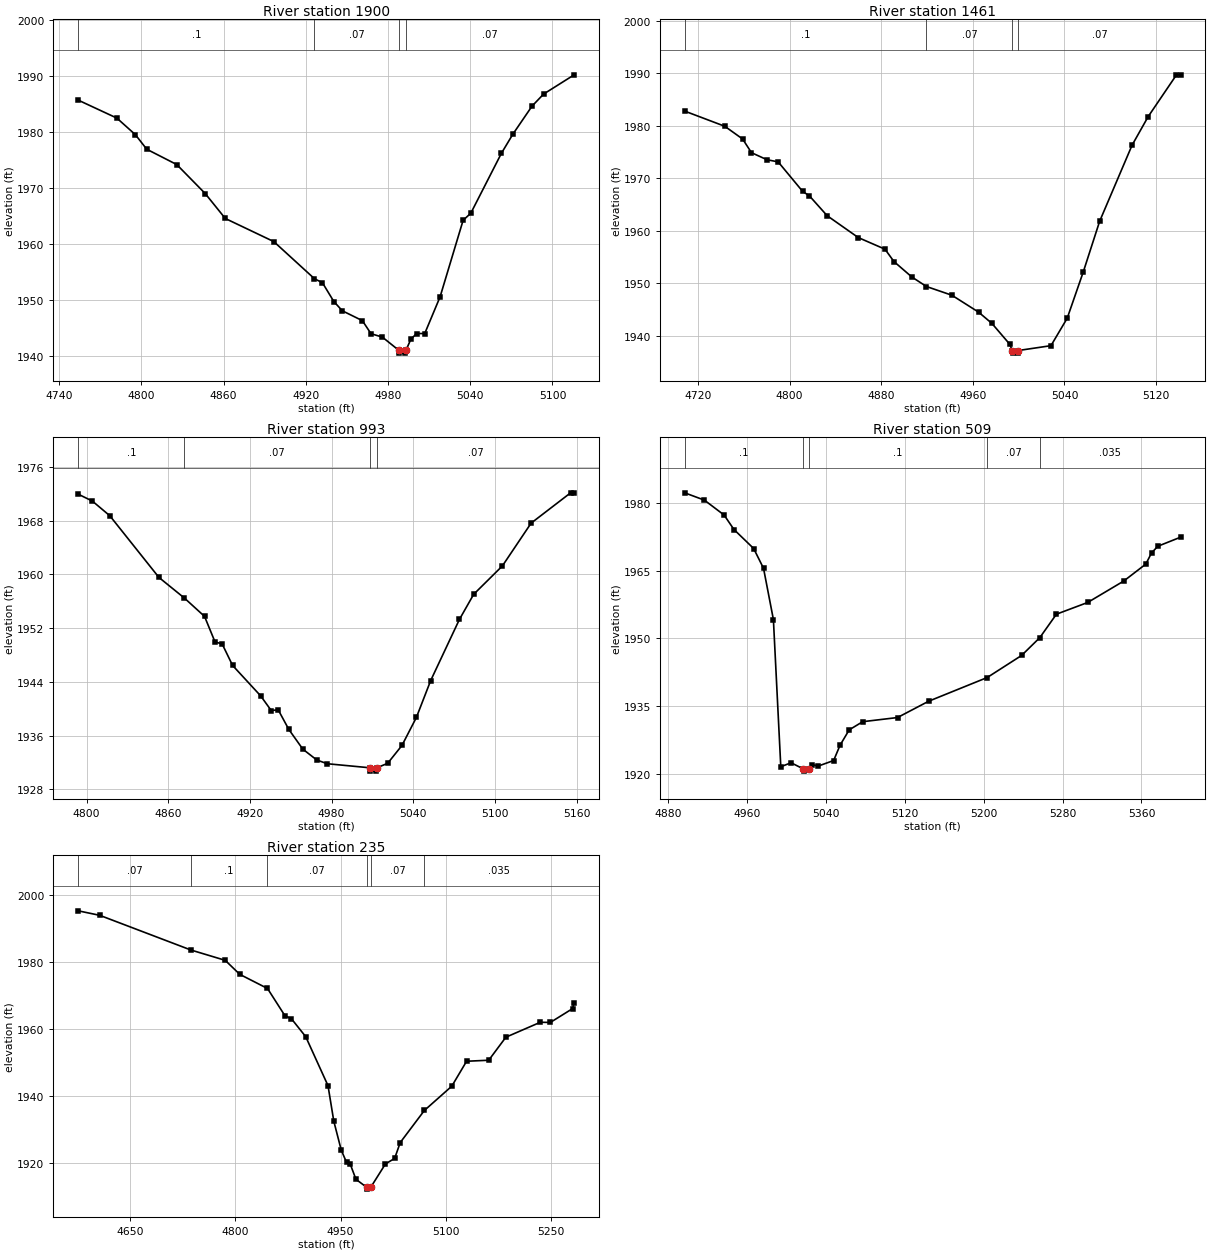
Type RM Length L Ch R = 1,1900,439,439,439
BEGIN DESCRIPTION:
Stream0194 4.0
END DESCRIPTION:
XS GIS Cut Line= 3
      1829725.02     13941774.97      1829575.00     13941975.00
      1829525.02     13942074.96
#Sta/Elev= 30
  4754.0 1985.77  4782.2 1982.56  4795.7 1979.60  4804.0 1977.00  4825.9 1974.26
  4846.7 1969.07  4861.3 1964.63  4896.7 1960.50  4926.3 1953.88  4932.2 1953.14
  4940.5 1949.79  4946.7 1948.14  4961.3 1946.38  4967.6 1944.05  4975.9 1943.44
  4987.9 1941.08  4988.3 1940.58  4992.7 1940.58  4993.1 1941.08  4996.7 1943.08
  5000.9 1944.08  5006.8 1944.08  5018.0 1950.64  5034.8 1964.31  5040.4 1965.57
  5062.7 1976.26  5071.1 1979.69  5085.1 1984.71  5093.5 1986.85  5115.8 1990.29
#Mann=4,-1,0
  4754.0     0.1       0  4926.3    0.07       0  4987.9    0.05       0
  4993.1    0.07       0
Bank Sta=4987.9,4993.1
Exp/Cntr=0.3,0.1

Type RM Length L Ch R = 1,1461,468,468,468
BEGIN DESCRIPTION:
Stream0194 3.0
END DESCRIPTION:
XS GIS Cut Line= 3
      1829525.01     13941524.99      1829275.00     13941675.00
      1829174.99     13941775.01
#Sta/Elev= 30
  4708.4 1982.79  4743.4 1979.90  4759.0 1977.47  4766.7 1974.87  4780.3 1973.52
  4790.0 1973.12  4811.4 1967.49  4817.3 1966.64  4832.8 1962.86  4860.0 1958.69
  4883.3 1956.48  4891.1 1954.13  4906.7 1951.19  4919.5 1949.37  4941.7 1947.71
  4965.0 1944.49  4976.6 1942.35  4992.2 1938.38  4994.4 1937.18  4994.8 1936.68
  4999.2 1936.68  4999.7 1937.18  5028.2 1938.10  5042.4 1943.34  5056.5 1952.21
  5070.7 1961.80  5099.0 1976.29  5113.1 1981.75  5137.8 1989.70  5141.4 1989.70
#Mann=4,-1,0
  4708.4     0.1       0  4919.5    0.07       0  4994.4    0.05       0
  4999.7    0.07       0
Bank Sta=4994.4,4999.7
Exp/Cntr=0.3,0.1

Type RM Length L Ch R = 1,993,484,484,484
BEGIN DESCRIPTION:
Stream0194 2.0
END DESCRIPTION:
XS GIS Cut Line= 3
      1829375.04     13941224.99      1829175.00     13941275.00
      1829025.01     13941325.00
#Sta/Elev= 30
  4793.9 1971.96  4804.3 1970.93  4817.1 1968.75  4853.2 1959.56  4871.9 1956.49
  4886.7 1953.76  4894.4 1949.95  4899.6 1949.67  4907.3 1946.46  4927.9 1941.93
  4935.7 1939.74  4940.8 1939.85  4948.6 1936.93  4958.9 1933.99  4969.2 1932.37
  4976.9 1931.82  5008.0 1931.22  5008.4 1930.72  5012.9 1930.72  5013.3 1931.22
  5021.2 1931.88  5031.7 1934.54  5042.3 1938.71  5052.8 1944.20  5073.9 1953.30
  5084.4 1957.05  5105.5 1961.28  5126.6 1967.65  5155.6 1972.16  5158.2 1972.16
#Mann=4,-1,0
  4793.9     0.1       0  4871.9    0.07       0  5008.0    0.05       0
  5013.3    0.07       0
Bank Sta=5008,5013.3
Exp/Cntr=0.3,0.1

Type RM Length L Ch R = 1,509,274,274,274
BEGIN DESCRIPTION:
Stream0194 1.0
END DESCRIPTION:
XS GIS Cut Line= 3
      1829075.00     13940725.03      1829075.00     13940825.00
      1828874.99     13941175.02
#Sta/Elev= 30
  4896.6 1982.29  4916.6 1980.67  4936.6 1977.36  4946.6 1974.15  4966.6 1969.93
  4976.6 1965.53  4986.6 1954.18  4994.1 1921.51  5004.5 1922.40  5016.9 1921.04
  5017.4 1920.54  5022.3 1921.04  5026.1 1922.00  5031.8 1921.64  5047.7 1922.89
  5054.2 1926.28  5063.5 1929.70  5077.2 1931.51  5112.5 1932.43  5144.1 1936.05
  5203.5 1941.31  5238.4 1946.21  5256.9 1950.17  5273.7 1955.36  5305.4 1957.96
  5342.1 1962.73  5364.4 1966.48  5370.2 1968.95  5376.6 1970.44  5399.7 1972.45
#Mann=5,-1,0
  4896.6     0.1       0  5016.9    0.05       0  5022.3     0.1       0
  5203.5    0.07       0  5256.9   0.035       0
Bank Sta=5016.9,5022.3
Exp/Cntr=0.3,0.1

Type RM Length L Ch R = 1,235,0,0,0
BEGIN DESCRIPTION:
Stream0194 0.0
END DESCRIPTION:
XS GIS Cut Line= 3
      1829109.08     13940524.96      1828865.42     13940707.47
      1828738.86     13941090.89
#Sta/Elev= 30
  4575.4 1995.19  4606.1 1993.85  4736.3 1983.49  4785.3 1980.41  4806.1 1976.22
  4845.7 1972.00  4870.7 1963.83  4879.8 1962.98  4900.3 1957.60  4932.1 1942.98
  4940.4 1932.34  4951.0 1923.74  4958.6 1920.05  4963.8 1919.58  4972.0 1915.02
  4987.6 1912.58  4988.1 1912.08  4993.0 1912.58  5014.1 1919.60  5027.3 1921.26
  5035.2 1925.98  5069.7 1935.57  5108.9 1942.83  5130.0 1950.27  5161.6 1950.57
  5186.1 1957.45  5235.3 1961.91  5249.6 1961.86  5281.3 1965.98  5283.6 1967.69
#Mann=6,-1,0
  4575.4    0.07       0  4736.3     0.1       0  4845.7    0.07       0
  4987.6    0.05       0  4993.0    0.07       0  5069.7   0.035       0
Bank Sta=4987.6,4993
Exp/Cntr=0.3,0.1

Chan Stop Cuts=-1