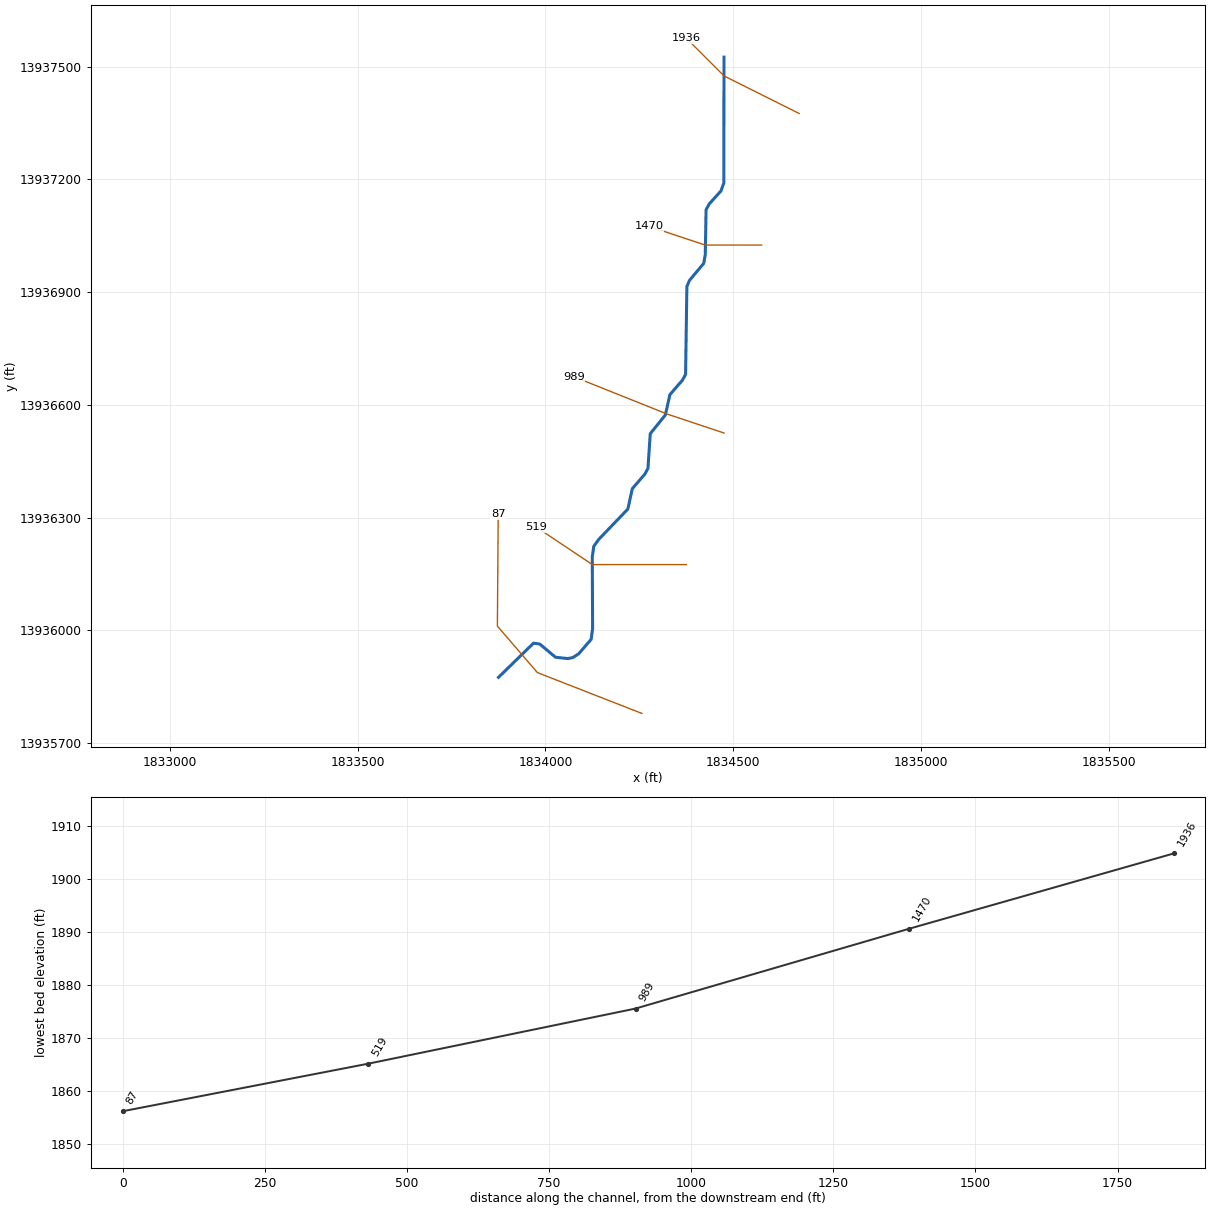
--- Stream0196.prj (project) ---

Proj Title=Stream0196 Base Level Engineering
Current Plan=p01
Default Exp/Contr=0.3,0.1
English Units
Geom File=g01
Flow File=f01
Plan File=p01
BEGIN DESCRIPTION:
Stream0196
END DESCRIPTION:

--- Stream0196.p01 (plan) ---

Plan Title=Multiple Run
Short Identifier=Multiple
Geom File=g01
Flow File=f01
Subcritical Flow
K Sum by GR= 0
Std Step Tol= 0.01
Critical Tol= 0.01
Num of Std Step Trials= 20
Max Error Tol= 0.3
Flow Tol Ratio= 0.001
Split Flow NTrial= 30
Split Flow Tol= 0.02
Split Flow Ratio= 0.02
Log Output Level= 0
Friction Slope Method= 1
Unsteady Friction Slope Method= 2
Unsteady Bridges Friction Slope Method= 1
Parabolic Critical Depth
Global Vel Dist=  1 , 1 , 1
Global Log Level= 0
CheckData=True
Encroach Param= -1, 0, 0, 0
BEGIN DESCRIPTION:
Multiple Run
END DESCRIPTION:

--- Stream0196.f01 (steady flow) ---

Flow Title=Multiple
Number of Profiles=7
Profile Names=10-year,25-year,50-year,1pct_min,100-year,1pct_plu,500-year
River Rch & RM= Stream0196,Reach-1,1936
     592     987    1356     905    1806    3604    3155
Boundary for River Rch & Prof#=Stream0196,Reach-1,1
Up Type=0
Dn Type=3
Dn Slope=0.005
Boundary for River Rch & Prof#=Stream0196,Reach-1,2
Up Type=0
Dn Type=3
Dn Slope=0.005
Boundary for River Rch & Prof#=Stream0196,Reach-1,3
Up Type=0
Dn Type=3
Dn Slope=0.005
Boundary for River Rch & Prof#=Stream0196,Reach-1,4
Up Type=0
Dn Type=3
Dn Slope=0.005
Boundary for River Rch & Prof#=Stream0196,Reach-1,5
Up Type=0
Dn Type=3
Dn Slope=0.005
Boundary for River Rch & Prof#=Stream0196,Reach-1,6
Up Type=0
Dn Type=3
Dn Slope=0.005
Boundary for River Rch & Prof#=Stream0196,Reach-1,7
Up Type=0
Dn Type=3
Dn Slope=0.005

--- Stream0196.g01 (geometry) ---

Geom Title=Existing Conditions

River Reach=Stream0196,Reach-1
Reach XY= 30
      1834475.00     13937525.00      1834474.48     13937190.22
      1834466.86     13937168.94      1834435.86     13937134.64
      1834427.27     13937119.06      1834425.18     13936999.93
      1834421.21     13936976.57      1834383.14     13936931.06
      1834376.22     13936914.50      1834372.76     13936680.93
      1834364.20     13936665.33      1834331.12     13936627.18
      1834318.89     13936572.82      1834278.83     13936523.42
      1834272.67     13936430.97      1834264.16     13936415.35
      1834231.14     13936377.17      1834219.15     13936322.71
      1834141.46     13936241.75      1834128.55     13936223.53
      1834124.57     13936195.18      1834125.46     13936004.74
      1834121.55     13935976.19      1834088.63     13935937.96
      1834073.60     13935928.06      1834059.78     13935924.95
      1834026.68     13935928.56      1833984.87     13935963.63
      1833968.27     13935965.99      1833875.00     13935875.00

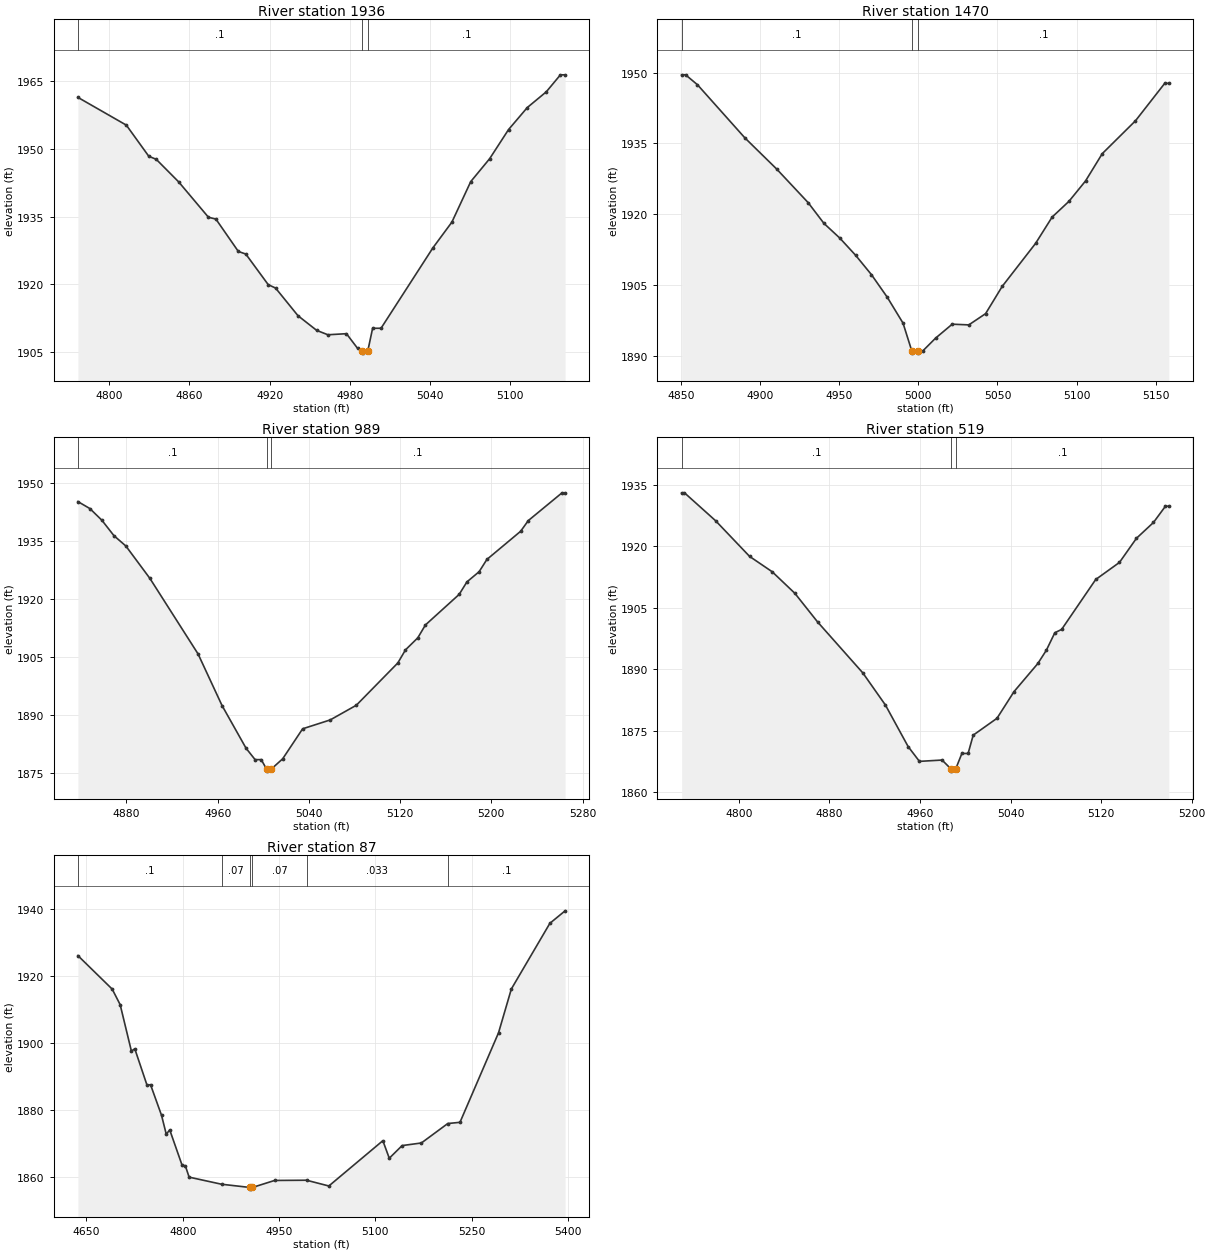
Type RM Length L Ch R = 1,1936,466,466,466
BEGIN DESCRIPTION:
Stream0196 4.0
END DESCRIPTION:
XS GIS Cut Line= 3
      1834675.00     13937375.00      1834475.00     13937475.00
      1834375.02     13937574.98
#Sta/Elev= 30
  4776.4 1961.36  4812.7 1955.22  4829.5 1948.34  4835.1 1947.66  4851.9 1942.67
  4874.2 1934.85  4879.8 1934.44  4896.6 1927.29  4902.2 1926.71  4919.0 1919.94
  4924.5 1919.19  4941.3 1913.07  4955.3 1909.83  4963.7 1908.86  4977.6 1909.10
  4986.0 1905.83  4989.6 1905.30  4989.9 1904.80  4993.6 1905.30  4997.2 1910.30
  5003.5 1910.30  5042.4 1928.10  5056.6 1933.78  5070.7 1942.73  5084.9 1947.81
  5099.0 1954.23  5113.1 1959.12  5127.3 1962.59  5137.9 1966.35  5141.4 1966.35
#Mann=3,-1,0
  4776.4     0.1       0  4989.6    0.05       0  4993.6     0.1       0
Bank Sta=4989.6,4993.6
Exp/Cntr=0.3,0.1

Type RM Length L Ch R = 1,1470,481,481,481
BEGIN DESCRIPTION:
Stream0196 3.0
END DESCRIPTION:
XS GIS Cut Line= 3
      1834575.01     13937025.00      1834425.00     13937025.00
      1834275.02     13937074.99
#Sta/Elev= 30
  4850.3 1949.54  4852.8 1949.54  4860.3 1947.44  4890.3 1936.18  4910.3 1929.62
  4930.3 1922.47  4940.3 1918.07  4950.3 1914.97  4960.3 1911.33  4970.3 1907.23
  4980.3 1902.45  4990.3 1896.95  4995.8 1891.10  4996.1 1890.60  4999.6 1890.60
  4999.8 1891.10  5002.9 1891.10  5010.9 1893.78  5021.4 1896.73  5031.9 1896.58
  5042.5 1898.96  5053.0 1904.73  5074.1 1913.83  5084.6 1919.42  5095.2 1922.74
  5105.7 1927.06  5116.3 1932.85  5137.3 1939.81  5155.8 1947.74  5158.4 1947.74
#Mann=3,-1,0
  4850.3     0.1       0  4995.8    0.05       0  4999.8     0.1       0
Bank Sta=4995.8,4999.8
Exp/Cntr=0.3,0.1

Type RM Length L Ch R = 1,989,470,470,470
BEGIN DESCRIPTION:
Stream0196 2.0
END DESCRIPTION:
XS GIS Cut Line= 3
      1834474.95     13936525.02      1834325.00     13936575.00
      1834075.02     13936674.99
#Sta/Elev= 30
  4837.4 1945.11  4847.9 1943.31  4858.4 1940.31  4869.0 1936.32  4879.5 1933.64
  4900.6 1925.27  4942.8 1905.80  4963.8 1892.50  4984.9 1881.47  4992.8 1878.54
  4998.2 1878.54  5002.9 1876.07  5003.1 1875.57  5006.9 1876.07  5017.0 1878.75
  5034.5 1886.49  5058.7 1888.78  5081.6 1892.57  5118.0 1903.48  5124.7 1906.85
  5135.5 1909.96  5142.2 1913.28  5171.8 1921.17  5178.6 1924.39  5189.3 1927.02
  5196.1 1930.18  5225.7 1937.45  5232.4 1940.20  5262.0 1947.37  5264.7 1947.37
#Mann=3,-1,0
  4837.4     0.1       0  5002.9    0.05       0  5006.9     0.1       0
Bank Sta=5002.9,5006.9
Exp/Cntr=0.3,0.1

Type RM Length L Ch R = 1,519,432,432,432
BEGIN DESCRIPTION:
Stream0196 1.0
END DESCRIPTION:
XS GIS Cut Line= 3
      1834374.99     13936175.00      1834125.00     13936175.00
      1833974.98     13936275.02
#Sta/Elev= 30
  4749.5 1933.04  4752.0 1933.04  4779.5 1926.23  4809.5 1917.54  4829.5 1913.79
  4849.5 1908.54  4869.5 1901.58  4909.5 1889.14  4929.5 1881.29  4949.5 1871.19
  4959.5 1867.57  4979.5 1867.89  4987.5 1865.69  4987.7 1865.19  4991.5 1865.69
  4997.0 1869.50  5002.5 1869.50  5007.0 1873.96  5028.0 1878.07  5043.1 1884.59
  5064.1 1891.43  5071.6 1894.66  5079.1 1898.93  5085.1 1899.74  5115.2 1911.91
  5136.2 1916.08  5151.2 1921.96  5166.2 1925.81  5176.8 1929.78  5179.8 1929.78
#Mann=3,-1,0
  4749.5     0.1       0  4987.5    0.05       0  4991.5     0.1       0
Bank Sta=4987.5,4991.5
Exp/Cntr=0.3,0.1

Type RM Length L Ch R = 1,87,0,0,0
BEGIN DESCRIPTION:
Stream0196 0.0
END DESCRIPTION:
XS GIS Cut Line= 4
      1834256.29     13935779.21      1833978.48     13935887.73
      1833872.14     13936011.43      1833874.31     13936308.74
#Sta/Elev= 30
  4636.7 1926.00  4690.1 1915.99  4702.5 1911.35  4720.0 1897.47  4725.3 1898.15
  4744.4 1887.25  4749.8 1887.44  4766.9 1878.30  4774.3 1872.64  4779.7 1873.93
  4798.8 1863.46  4804.1 1863.15  4809.9 1859.81  4860.5 1857.69  4904.5 1856.73
  4904.7 1856.23  4908.5 1856.73  4943.0 1858.82  4992.7 1858.89  5027.5 1857.17
  5111.6 1870.70  5121.6 1865.46  5141.6 1869.24  5171.6 1870.02  5212.7 1875.83
  5231.7 1876.19  5291.7 1902.92  5311.7 1916.03  5371.7 1935.65  5395.4 1939.38
#Mann=6,-1,0
  4636.7     0.1       0  4860.5    0.07       0  4904.5   0.033       0
  4908.5    0.07       0  4992.7   0.033       0  5212.7     0.1       0
Bank Sta=4904.5,4908.5
Exp/Cntr=0.3,0.1

Chan Stop Cuts=-1