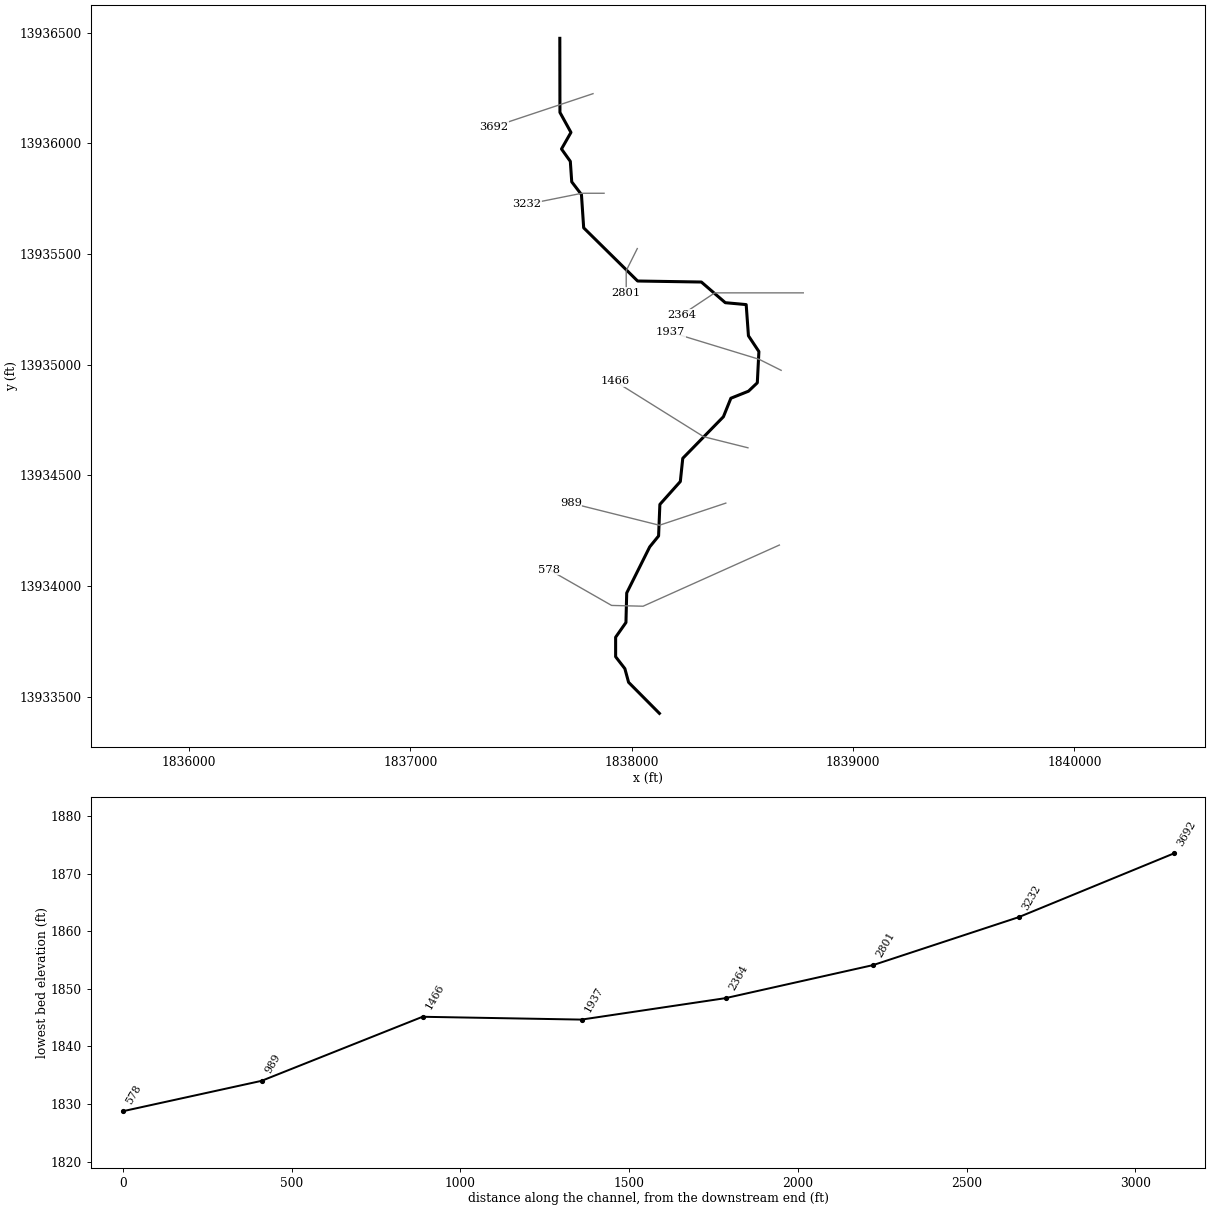
--- Stream0197.prj (project) ---

Proj Title=Stream0197 Base Level Engineering
Current Plan=p01
Default Exp/Contr=0.3,0.1
English Units
Geom File=g01
Flow File=f01
Plan File=p01
BEGIN DESCRIPTION:
Stream0197
END DESCRIPTION:

--- Stream0197.p01 (plan) ---

Plan Title=Multiple Run
Short Identifier=Multiple
Geom File=g01
Flow File=f01
Subcritical Flow
K Sum by GR= 0
Std Step Tol= 0.01
Critical Tol= 0.01
Num of Std Step Trials= 20
Max Error Tol= 0.3
Flow Tol Ratio= 0.001
Split Flow NTrial= 30
Split Flow Tol= 0.02
Split Flow Ratio= 0.02
Log Output Level= 0
Friction Slope Method= 1
Unsteady Friction Slope Method= 2
Unsteady Bridges Friction Slope Method= 1
Parabolic Critical Depth
Global Vel Dist=  1 , 1 , 1
Global Log Level= 0
CheckData=True
Encroach Param= -1, 0, 0, 0
BEGIN DESCRIPTION:
Multiple Run
END DESCRIPTION:

--- Stream0197.f01 (steady flow) ---

Flow Title=Multiple
Number of Profiles=7
Profile Names=10-year,25-year,50-year,1pct_min,100-year,1pct_plu,500-year
River Rch & RM= Stream0197,Reach-1,3692
    2062    3676    5276    3653    7289   14544   13765
Boundary for River Rch & Prof#=Stream0197,Reach-1,1
Up Type=0
Dn Type=3
Dn Slope=0.005
Boundary for River Rch & Prof#=Stream0197,Reach-1,2
Up Type=0
Dn Type=3
Dn Slope=0.005
Boundary for River Rch & Prof#=Stream0197,Reach-1,3
Up Type=0
Dn Type=3
Dn Slope=0.005
Boundary for River Rch & Prof#=Stream0197,Reach-1,4
Up Type=0
Dn Type=3
Dn Slope=0.005
Boundary for River Rch & Prof#=Stream0197,Reach-1,5
Up Type=0
Dn Type=3
Dn Slope=0.005
Boundary for River Rch & Prof#=Stream0197,Reach-1,6
Up Type=0
Dn Type=3
Dn Slope=0.005
Boundary for River Rch & Prof#=Stream0197,Reach-1,7
Up Type=0
Dn Type=3
Dn Slope=0.005

--- Stream0197.g01 (geometry) ---

Geom Title=Existing Conditions

River Reach=Stream0197,Reach-1
Reach XY= 30
      1837675.00     13936475.00      1837675.54     13936140.21
      1837725.31     13936049.96      1837682.59     13935975.01
      1837722.45     13935919.11      1837728.85     13935826.60
      1837772.73     13935769.06      1837782.82     13935618.81
      1838026.46     13935378.54      1838314.56     13935373.94
      1838422.65     13935280.57      1838517.05     13935271.99
      1838527.28     13935130.95      1838574.49     13935059.78
      1838567.31     13934918.53      1838527.55     13934880.75
      1838447.87     13934848.83      1838414.21     13934765.34
      1838230.52     13934577.43      1838219.46     13934472.58
      1838127.08     13934369.14      1838121.24     13934226.56
      1838081.12     13934177.18      1837977.25     13933969.07
      1837973.77     13933835.51      1837927.17     13933769.02
      1837927.14     13933680.97      1837968.85     13933627.17
      1837985.76     13933565.31      1838125.00     13933425.00

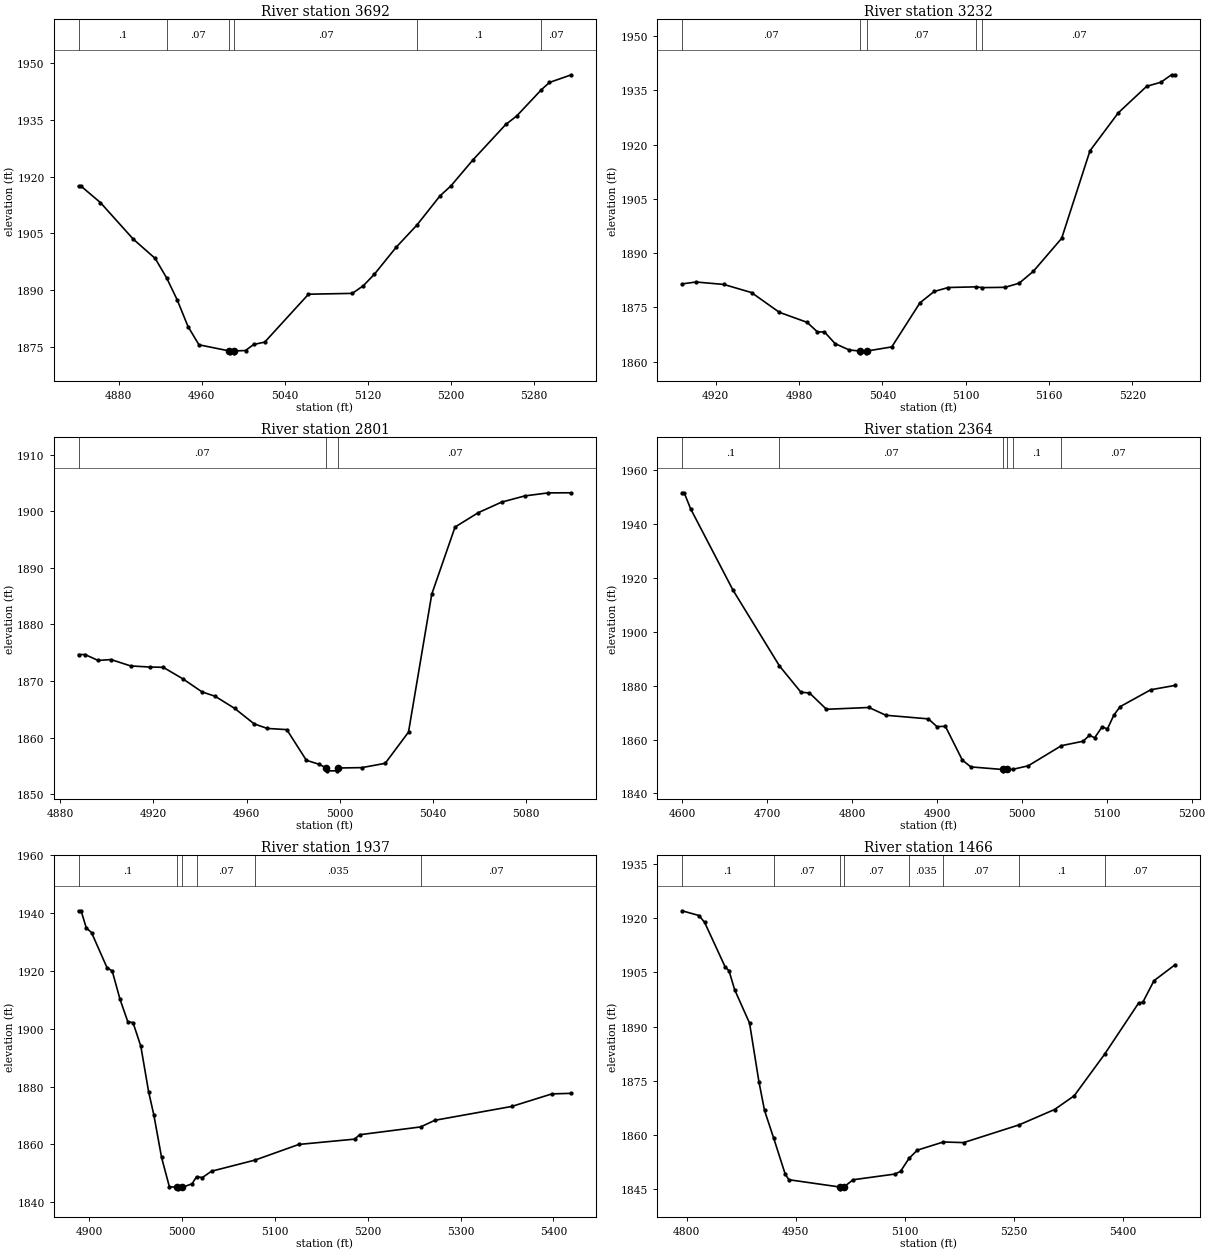
Type RM Length L Ch R = 1,3692,460,460,460
BEGIN DESCRIPTION:
Stream0197 8.0
END DESCRIPTION:
XS GIS Cut Line= 3
      1837824.99     13936225.00      1837675.00     13936175.00
      1837375.03     13936075.01
#Sta/Elev= 30
  4841.5 1917.44  4844.1 1917.44  4862.6 1913.15  4894.2 1903.51  4915.3 1898.42
  4926.3 1893.29  4936.4 1887.54  4946.9 1880.46  4957.4 1875.65  4986.6 1874.03
  4986.9 1873.53  4991.2 1873.53  4991.6 1874.03  5002.2 1874.14  5010.1 1875.74
  5020.7 1876.36  5062.8 1888.99  5105.0 1889.21  5115.6 1891.24  5126.1 1894.22
  5147.2 1901.38  5167.1 1907.21  5189.3 1914.90  5199.9 1917.56  5221.0 1924.39
  5252.6 1933.74  5263.1 1935.97  5286.9 1942.91  5294.7 1944.83  5315.8 1946.85
#Mann=6,-1,0
  4841.5     0.1       0  4926.3    0.07       0  4986.6    0.05       0
  4991.6    0.07       0  5167.1     0.1       0  5286.9    0.07       0
Bank Sta=4986.6,4991.6
Exp/Cntr=0.3,0.1

Type RM Length L Ch R = 1,3232,431,431,431
BEGIN DESCRIPTION:
Stream0197 7.0
END DESCRIPTION:
XS GIS Cut Line= 3
      1837874.96     13935775.00      1837775.00     13935775.00
      1837525.01     13935725.00
#Sta/Elev= 30
  4895.8 1881.50  4905.8 1882.03  4925.8 1881.36  4945.8 1879.11  4965.8 1873.66
  4985.8 1870.88  4993.3 1868.23  4998.3 1868.23  5006.0 1864.99  5016.2 1863.24
  5023.9 1862.95  5024.2 1862.45  5028.5 1862.45  5028.9 1862.95  5046.8 1864.09
  5067.1 1876.28  5077.3 1879.41  5087.5 1880.51  5107.3 1880.69  5112.1 1880.48
  5128.3 1880.56  5138.5 1881.70  5148.7 1884.98  5169.1 1894.09  5189.5 1918.31
  5209.9 1928.80  5230.3 1936.12  5240.5 1937.24  5248.2 1939.31  5250.7 1939.31
#Mann=5,-1,0
  4895.8    0.07       0  5023.9    0.05       0  5028.9    0.07       0
  5107.3     0.1       0  5112.1    0.07       0
Bank Sta=5023.9,5028.9
Exp/Cntr=0.3,0.1

Type RM Length L Ch R = 1,2801,437,437,437
BEGIN DESCRIPTION:
Stream0197 6.0
END DESCRIPTION:
XS GIS Cut Line= 3
      1838025.02     13935525.03      1837975.00     13935425.00
      1837975.00     13935325.04
#Sta/Elev= 30
  4887.8 1874.67  4890.6 1874.67  4896.2 1873.63  4901.8 1873.78  4910.2 1872.66
  4918.6 1872.46  4924.2 1872.42  4932.6 1870.39  4940.9 1868.07  4946.5 1867.30
  4954.9 1865.16  4963.3 1862.42  4968.9 1861.62  4977.3 1861.41  4985.7 1856.00
  4991.3 1855.27  4994.3 1854.63  4994.7 1854.13  4999.0 1854.13  4999.4 1854.63
  5009.6 1854.70  5019.6 1855.46  5029.6 1860.97  5039.6 1885.34  5049.6 1897.19
  5059.6 1899.73  5069.6 1901.59  5079.6 1902.69  5089.6 1903.22  5099.6 1903.24
#Mann=3,-1,0
  4887.8    0.07       0  4994.3    0.05       0  4999.4    0.07       0
Bank Sta=4994.3,4999.4
Exp/Cntr=0.3,0.1

Type RM Length L Ch R = 1,2364,427,427,427
BEGIN DESCRIPTION:
Stream0197 5.0
END DESCRIPTION:
XS GIS Cut Line= 3
      1838775.02     13935325.00      1838375.00     13935325.00
      1838225.00     13935225.00
#Sta/Elev= 30
  4600.0 1951.61  4602.5 1951.61  4610.0 1945.70  4660.0 1915.44  4714.7 1887.31
  4740.0 1877.56  4750.0 1877.30  4770.0 1871.24  4820.0 1871.91  4840.0 1869.02
  4890.0 1867.68  4900.0 1864.81  4910.0 1864.92  4930.0 1852.35  4940.0 1849.85
  4977.4 1848.89  4977.8 1848.39  4982.6 1848.89  4989.2 1848.94  5007.5 1850.25
  5046.6 1857.73  5072.1 1859.38  5079.6 1861.57  5085.7 1860.66  5094.7 1864.79
  5100.7 1863.88  5108.2 1869.01  5115.7 1872.21  5151.8 1878.49  5180.3 1880.10
#Mann=6,-1,0
  4600.0     0.1       0  4714.7    0.07       0  4977.4    0.05       0
  4982.6    0.07       0  4989.2     0.1       0  5046.6    0.07       0
Bank Sta=4977.4,4982.6
Exp/Cntr=0.3,0.1

Type RM Length L Ch R = 1,1937,471,471,471
BEGIN DESCRIPTION:
Stream0197 4.0
END DESCRIPTION:
XS GIS Cut Line= 3
      1838675.00     13934975.00      1838575.00     13935025.00
      1838174.41     13935147.49
#Sta/Elev= 30
  4888.7 1940.83  4891.5 1940.83  4897.1 1934.88  4902.7 1933.31  4919.4 1921.16
  4925.0 1920.00  4933.4 1910.21  4941.8 1902.45  4947.4 1902.15  4955.8 1893.99
  4964.2 1878.22  4969.8 1870.25  4978.1 1855.57  4986.5 1845.42  4995.1 1845.16
  4995.5 1844.66  5000.4 1845.16  5011.0 1846.42  5015.8 1848.85  5022.1 1848.57
  5031.9 1850.75  5078.8 1854.61  5126.0 1860.02  5186.0 1861.85  5191.3 1863.37
  5257.0 1866.07  5272.4 1868.37  5355.2 1873.16  5398.4 1877.50  5419.4 1877.69
#Mann=6,-1,0
  4888.7     0.1       0  4995.1    0.05       0  5000.4     0.1       0
  5015.8    0.07       0  5078.8   0.035       0  5257.0    0.07       0
Bank Sta=4995.1,5000.4
Exp/Cntr=0.3,0.1

Type RM Length L Ch R = 1,1466,477,477,477
BEGIN DESCRIPTION:
Stream0197 3.0
END DESCRIPTION:
XS GIS Cut Line= 3
      1838525.03     13934624.99      1838325.00     13934675.00
      1837924.99     13934925.01
#Sta/Elev= 30
  4793.8 1922.01  4817.0 1920.70  4824.8 1918.81  4853.1 1906.47  4858.3 1905.46
  4866.0 1900.25  4886.6 1890.96  4899.5 1874.75  4907.2 1866.81  4919.6 1859.28
  4935.6 1849.24  4940.7 1847.67  5010.9 1845.65  5011.3 1845.15  5016.3 1845.65
  5028.9 1847.66  5086.7 1849.24  5094.3 1849.99  5105.8 1853.54  5117.3 1855.84
  5153.1 1858.10  5181.0 1857.93  5257.4 1862.84  5306.0 1867.07  5333.1 1870.87
  5374.9 1882.36  5421.6 1896.48  5427.5 1896.74  5442.8 1902.68  5471.7 1907.07
#Mann=8,-1,0
  4793.8     0.1       0  4919.6    0.07       0  5010.9    0.05       0
  5016.3    0.07       0  5105.8   0.035       0  5153.1    0.07       0
  5257.4     0.1       0  5374.9    0.07       0
Bank Sta=5010.9,5016.3
Exp/Cntr=0.3,0.1

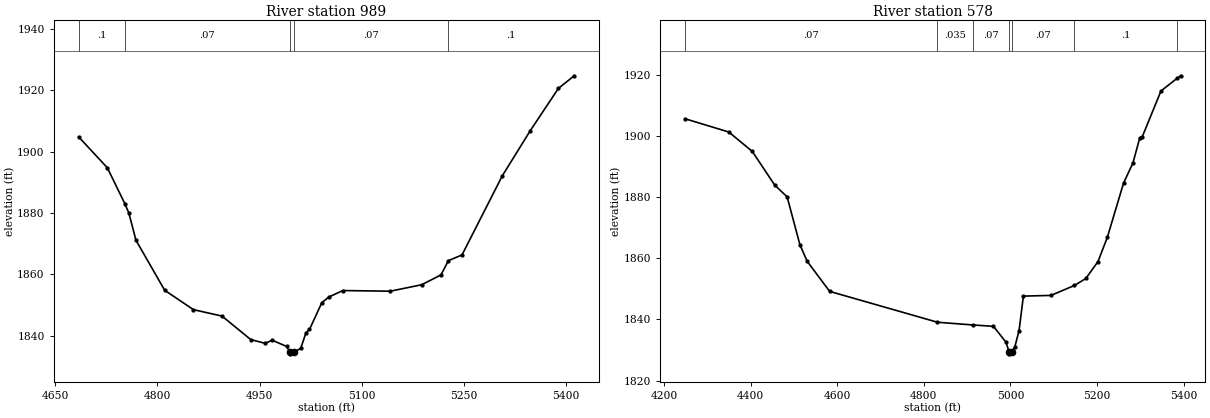
Type RM Length L Ch R = 1,989,411,411,411
BEGIN DESCRIPTION:
Stream0197 2.0
END DESCRIPTION:
XS GIS Cut Line= 3
      1838425.00     13934375.00      1838125.00     13934275.00
      1837725.04     13934374.99
#Sta/Elev= 30
  4684.1 1904.80  4726.3 1894.72  4751.9 1883.06  4757.9 1879.98  4768.4 1871.06
  4810.6 1854.76  4852.8 1848.44  4894.9 1846.33  4937.1 1838.68  4958.2 1837.46
  4968.7 1838.45  4989.8 1836.44  4994.9 1834.52  4995.4 1834.02  5000.4 1834.52
  5010.6 1835.80  5018.4 1840.94  5023.5 1841.97  5041.6 1850.71  5051.9 1852.55
  5072.5 1854.67  5142.1 1854.45  5188.4 1856.56  5216.8 1859.77  5227.7 1864.43
  5247.7 1866.28  5307.0 1892.12  5348.2 1906.87  5389.4 1920.61  5412.6 1924.73
#Mann=5,-1,0
  4684.1     0.1       0  4751.9    0.07       0  4994.9    0.05       0
  5000.4    0.07       0  5227.7     0.1       0
Bank Sta=4994.9,5000.4
Exp/Cntr=0.3,0.1

Type RM Length L Ch R = 1,578,0,0,0
BEGIN DESCRIPTION:
Stream0197 1.0
END DESCRIPTION:
XS GIS Cut Line= 4
      1838666.97     13934185.54      1838051.15     13933909.17
      1837908.98     13933912.73      1837624.98     13934075.01
#Sta/Elev= 30
  4248.7 1905.68  4349.5 1901.35  4403.8 1895.00  4455.6 1883.98  4484.3 1880.12
  4513.9 1864.41  4530.6 1859.03  4582.5 1849.18  4831.5 1839.08  4914.5 1838.18
  4960.8 1837.74  4989.9 1832.50  4997.1 1829.24  4997.6 1828.74  5002.6 1829.24
  5009.9 1830.91  5019.9 1836.36  5029.9 1847.64  5093.5 1847.86  5147.9 1851.13
  5174.1 1853.40  5202.2 1858.96  5223.8 1866.90  5261.2 1884.64  5282.8 1891.18
  5298.7 1899.48  5304.4 1899.79  5347.6 1914.78  5385.7 1919.02  5393.0 1919.75
#Mann=7,-1,0
  4248.7    0.07       0  4831.5   0.035       0  4914.5    0.07       0
  4997.1    0.05       0  5002.6    0.07       0  5147.9     0.1       0
  5385.7    0.07       0
Bank Sta=4997.1,5002.6
Exp/Cntr=0.3,0.1

Chan Stop Cuts=-1