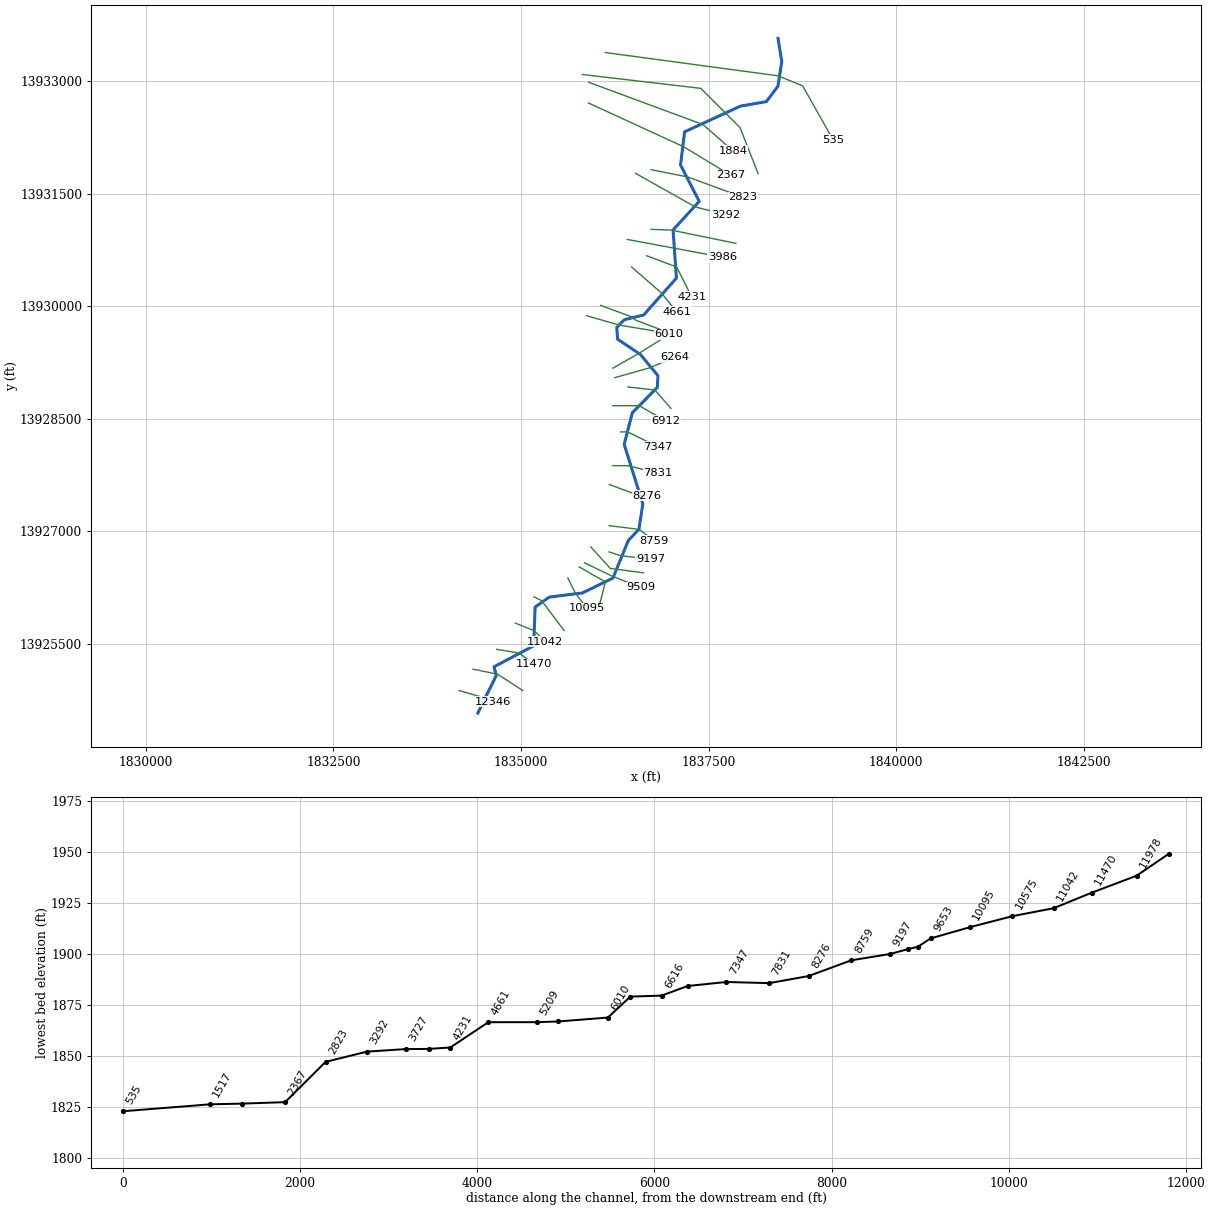
--- Stream0198.prj (project) ---

Proj Title=Stream0198 Base Level Engineering
Current Plan=p01
Default Exp/Contr=0.3,0.1
English Units
Geom File=g01
Flow File=f01
Plan File=p01
Y Axis Title=Elevation
X Axis Title(PF)=Main Channel Distance
X Axis Title(XS)=Station
BEGIN DESCRIPTION:
Stream0198
END DESCRIPTION:
DSS Export Rating Curves= 0
DSS Export Rating Curve Sorted= 0
DSS Export Volume Flow Curves= 0
DXF OffsetX= 0
DXF OffsetY= 0
DXF ScaleX= 1
DXF ScaleY= 10

--- Stream0198.p01 (plan) ---

Plan Title=Multiple Run
Short Identifier=Multiple
Geom File=g01
Flow File=f01
Subcritical Flow
K Sum by GR= 0
Std Step Tol= 0.01
Critical Tol= 0.01
Num of Std Step Trials= 20
Max Error Tol= 0.3
Flow Tol Ratio= 0.001
Split Flow NTrial= 30
Split Flow Tol= 0.02
Split Flow Ratio= 0.02
Log Output Level= 0
Friction Slope Method= 1
Unsteady Friction Slope Method= 2
Unsteady Bridges Friction Slope Method= 1
Parabolic Critical Depth
Global Vel Dist=  1 , 1 , 1
Global Log Level= 0
CheckData=True
Encroach Param= -1, 0, 0, 0
BEGIN DESCRIPTION:
Multiple Run
END DESCRIPTION:

--- Stream0198.f01 (steady flow) ---

Flow Title=Multiple
Program Version=4.10
Number of Profiles= 7
Profile Names=10-year,25-year,50-year,1pct_min,100-year,1pct_plu,500-year
River Rch & RM=Stream0198,Reach-1         ,12346
    1802    3192    4562    3148    6281   12532   11775
River Rch & RM=Stream0198,Reach-1         ,9509
    2535    4564    6593    4591    9161   18278   17500
River Rch & RM=Stream0198,Reach-1         ,6264
    2645    4770    6897    4807    9591   19137   18355
River Rch & RM=Stream0198,Reach-1         ,5449
    2802    5064    7335    5120   10215   20382   19605
River Rch & RM=Stream0198,Reach-1         ,4661
    2880    5194    7512    5232   10440   20830   19957
Boundary for River Rch & Prof#=Stream0198,Reach-1         , 1
Up Type= 0
Dn Type= 3
Dn Slope=0.008
Boundary for River Rch & Prof#=Stream0198,Reach-1         , 2
Up Type= 0
Dn Type= 3
Dn Slope=0.008
Boundary for River Rch & Prof#=Stream0198,Reach-1         , 3
Up Type= 0
Dn Type= 3
Dn Slope=0.008
Boundary for River Rch & Prof#=Stream0198,Reach-1         , 4
Up Type= 0
Dn Type= 3
Dn Slope=0.008
Boundary for River Rch & Prof#=Stream0198,Reach-1         , 5
Up Type= 0
Dn Type= 3
Dn Slope=0.008
Boundary for River Rch & Prof#=Stream0198,Reach-1         , 6
Up Type= 0
Dn Type= 3
Dn Slope=0.008
Boundary for River Rch & Prof#=Stream0198,Reach-1         , 7
Up Type= 0
Dn Type= 3
Dn Slope=0.008
DSS Import GetInterval= 0
DSS Import GetPeak= 0
DSS Import FillOption= 0

--- Stream0198.g01 (geometry) ---

Geom Title=Existing Conditions
Program Version=4.10

River Reach=Stream0198      ,Reach-1
Reach XY= 30
        1834425.       13924575.      1834671.63     13925076.74
      1834641.15     13925192.08      1835169.64      13925472.3
      1835188.39     13925988.33      1835376.56     13926121.24
      1835819.07     13926177.24        1836225.       13926375.
      1836430.83      13926877.3      1836571.39      13927026.5
      1836623.78     13927364.49      1836375.38     13928159.73
       1836484.3     13928581.67      1836817.21      13928918.8
        1836825.       13929075.      1836591.75     13929358.54
      1836288.35     13929561.67      1836276.67     13929718.87
      1836376.45     13929821.47      1836635.25     13929885.33
      1837071.46     13930376.46      1837026.62     13931018.97
      1837375.51     13931399.96      1837126.04     13931885.44
      1837180.34     13932327.74      1837926.47     13932671.45
      1838269.53     13932730.26      1838423.95     13932935.43
      1838475.45     13933264.81        1838425.       13933575.

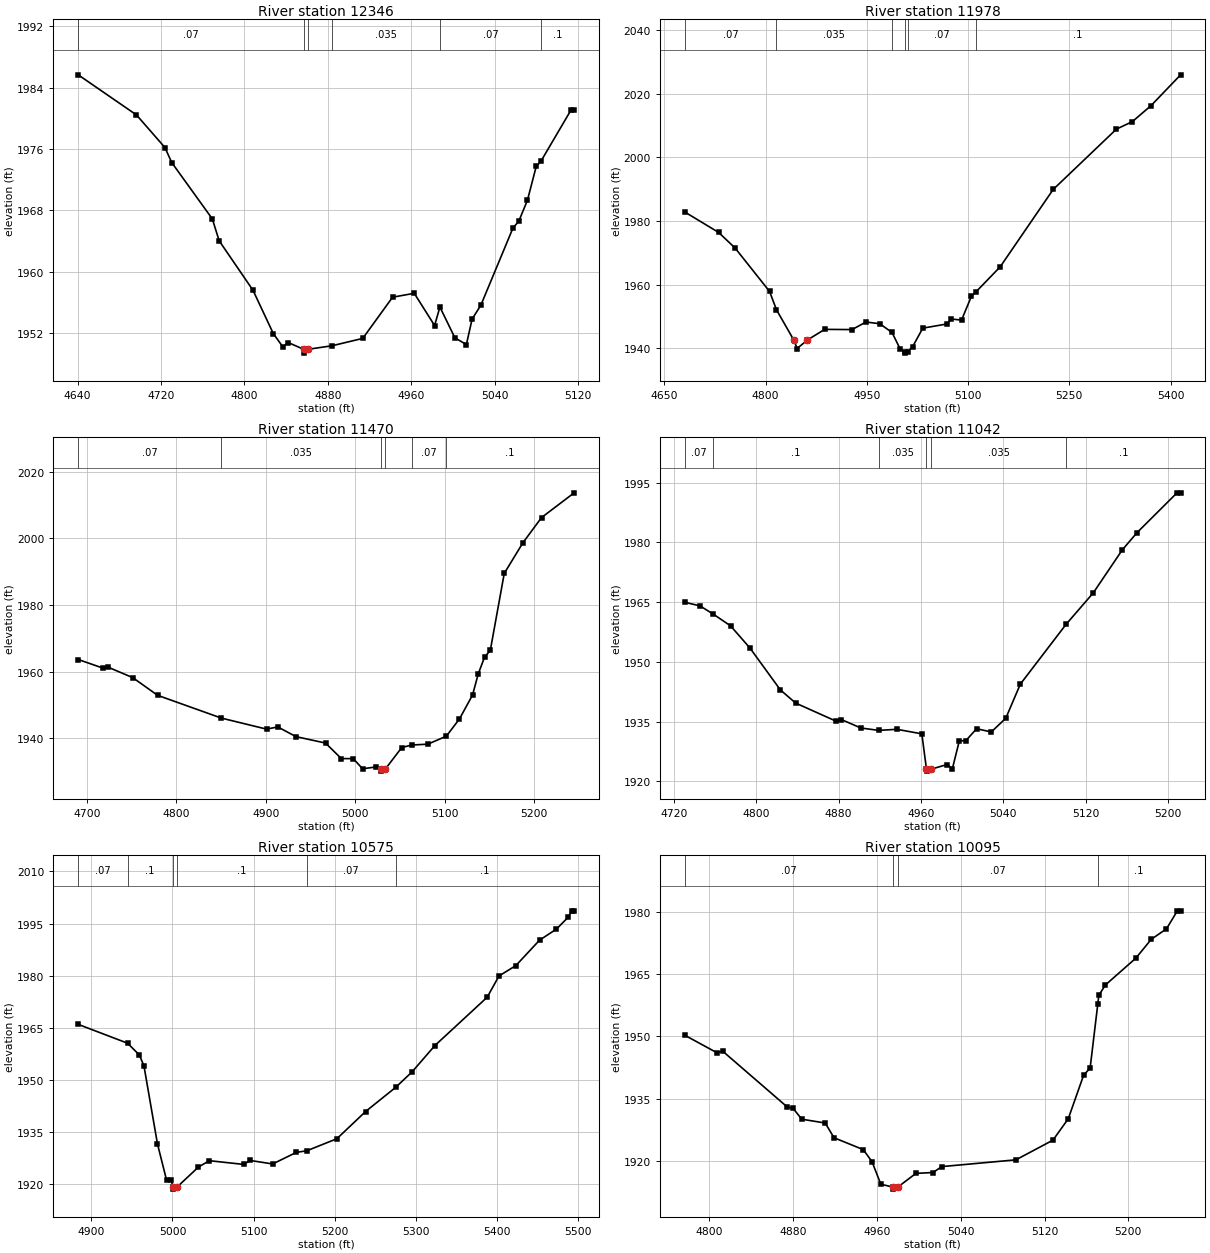
Type RM Length L Ch R = 1 ,12346   ,368,368,368
BEGIN DESCRIPTION:
Stream0198 25.0
END DESCRIPTION:
XS GIS Cut Line= 3
      1834175.04     13924874.99        1834525.       13924775.
      1834625.03     13924724.99
#Sta/Elev= 30
  4640.6 1985.66  4696.5 1980.43  4723.8 1976.18  4730.3 1974.23  4769.3 1966.87
  4775.8 1964.03  4808.3 1957.57  4827.8 1951.92  4836.9  1950.2  4842.1 1950.76
  4856.8 1949.88  4857.1 1949.38  4861.1 1949.88  4884.1 1950.34  4913.6  1951.3
  4942.2 1956.67    4963 1957.18  4982.5 1952.98  4987.6 1955.39    5002 1951.37
    5013  1950.5  5018.5 1953.82  5026.9 1955.63  5057.7 1965.69  5063.3 1966.58
  5071.6 1969.32    5080 1973.71  5084.5 1974.39  5113.6 1981.12  5116.4 1981.12
#Mann= 6 ,-1 , 0
  4640.6     .07       0  4856.8     .05       0  4861.1     .07       0
  4884.1    .035       0  4987.6     .07       0  5084.5      .1       0
Bank Sta=4856.8,4861.1
XS Rating Curve= 0 ,0
Exp/Cntr=0.3,0.1

Type RM Length L Ch R = 1 ,11978   ,508,508,508
BEGIN DESCRIPTION:
Stream0198 24.0
END DESCRIPTION:
XS GIS Cut Line= 3
      1834361.72     13925160.22      1834687.14     13925094.28
      1835024.99     13924875.01
#Sta/Elev= 30
  4680.1 1982.82  4730.5 1976.37  4754.9 1971.46  4805.9 1957.85  4816.1  1952.1
 4842.01  1942.5  4846.7 1939.93 4861.97 1942.62  4887.6 1945.95  4928.1 1945.88
  4948.7 1948.26  4969.1 1947.72  4987.3 1944.98  4999.7 1939.66  5006.3 1938.99
  5006.6 1938.49  5010.6 1938.99  5017.8  1940.5  5032.9 1946.33  5069.2 1947.66
  5075.1  1949.2  5090.3 1948.86    5105 1956.37    5111 1957.57  5147.6  1965.6
  5226.1 1989.88  5319.7 2008.81  5343.4 2011.18  5371.1 2016.21  5414.9 2025.87
#Mann= 6 ,-1 , 0
  4680.1     .07       0  4816.1    .035       0  4987.3     .07       0
  5006.3     .05       0  5010.6     .07       0    5111      .1       0
Bank Sta=4842.01,4861.97
XS Rating Curve= 0 ,0
Exp/Cntr=0.3,0.1

Type RM Length L Ch R = 1 ,11470   ,428,428,428
BEGIN DESCRIPTION:
Stream0198 23.0
END DESCRIPTION:
XS GIS Cut Line= 3
      1834674.99       13925425.        1834975.       13925375.
      1835174.96     13925225.03
#Sta/Elev= 30
  4690.4 1963.62  4718.3 1961.01  4723.4 1961.36  4751.2  1958.2  4779.1 1952.88
  4850.3 1946.05  4900.8 1942.74  4913.4 1943.39  4933.7 1940.49  4966.7 1938.56
  4984.4  1933.9  4997.7 1933.89  5008.1 1930.85  5022.7 1931.37  5028.8 1930.64
  5029.1 1930.14  5033.2 1930.64  5051.8 1937.19  5062.8 1937.97    5081 1938.22
  5101.7 1940.62  5116.4 1945.81    5131 1952.98  5137.3 1959.28  5144.5 1964.39
  5150.8 1966.32  5166.4 1989.45  5187.3 1998.65  5208.1  2006.2  5244.5 2013.61
#Mann= 6 ,-1 , 0
  4690.4     .07       0  4850.3    .035       0  5028.8    .035       0
  5033.2    .035       0  5062.8     .07       0  5101.7      .1       0
Bank Sta=5028.8,5033.2
XS Rating Curve= 0 ,0
Exp/Cntr=0.3,0.1

Type RM Length L Ch R = 1 ,11042   ,467,467,467
BEGIN DESCRIPTION:
Stream0198 22.0
END DESCRIPTION:
XS GIS Cut Line= 3
      1834924.98     13925775.01        1835175.       13925675.
      1835324.99     13925525.01
#Sta/Elev= 30
  4730.6 1964.94  4745.4 1964.04    4758 1962.02  4775.1 1959.03  4793.9 1953.47
  4823.5 1942.93  4838.3 1939.63  4877.4  1935.1  4882.8 1935.48  4901.6 1933.37
    4919 1932.77  4936.6 1933.04  4960.8  1931.9  4965.3 1923.04  4965.6 1922.54
  4969.9 1923.04  4985.1 1924.18  4990.5 1923.19  4997.2 1930.16  5003.4 1930.16
    5014 1933.19  5028.2 1932.37  5042.3 1935.82  5056.4 1944.38  5100.9 1959.43
  5127.2 1967.29  5155.4  1978.1  5169.6  1982.4  5208.5 1992.42    5212 1992.42
#Mann= 6 ,-1 , 0
  4730.6     .07       0    4758      .1       0    4919    .035       0
  4965.3    .035       0  4969.9    .035       0  5100.9      .1       0
Bank Sta=4965.3,4969.9
XS Rating Curve= 0 ,0
Exp/Cntr=0.3,0.1

Type RM Length L Ch R = 1 ,10575   ,480,480,480
BEGIN DESCRIPTION:
Stream0198 21.0
END DESCRIPTION:
XS GIS Cut Line= 3
      1835174.99     13926125.01        1835275.       13926075.
      1835574.99     13925675.01
#Sta/Elev= 30
  4883.7 1966.01  4944.6 1960.59  4959.2 1957.19  4964.8 1954.06  4981.5 1931.59
  4992.7  1921.2  4998.6  1921.2  5000.5 1919.12  5000.8 1918.62  5005.2 1919.12
    5032 1924.97  5045.5  1926.8  5088.2 1925.72  5095.5 1926.88  5123.6 1925.86
  5152.8 1929.19  5165.8 1929.66  5202.8 1933.12  5238.2 1940.94  5275.3 1947.89
  5295.5 1952.33  5323.6 1959.89  5388.2 1973.82  5402.8 1979.93  5423.6 1982.92
  5452.8 1990.23  5473.6 1993.41  5488.2 1996.84  5492.4 1998.67  5495.5 1998.67
#Mann= 6 ,-1 , 0
  4883.7     .07       0  4944.6      .1       0  5000.5     .05       0
  5005.2      .1       0  5165.8     .07       0  5275.3      .1       0
Bank Sta=5000.5,5005.2
XS Rating Curve= 0 ,0
Exp/Cntr=0.3,0.1

Type RM Length L Ch R = 1 ,10095   ,442,442,442
BEGIN DESCRIPTION:
Stream0198 20.0
END DESCRIPTION:
XS GIS Cut Line= 3
        1835625.       13926375.        1835725.       13926175.
      1835874.99     13925975.01
#Sta/Elev= 30
  4776.3 1950.25    4807 1946.04  4812.6  1946.4  4874.1    1933  4879.7 1932.68
  4888.1 1930.03  4910.5 1929.11  4918.9 1925.57  4946.8 1922.71  4955.2 1919.81
  4963.6 1914.38  4975.1  1913.7  4975.5  1913.2  4979.9  1913.7  4997.1 1916.99
  5013.5  1917.2  5021.8 1918.62  5092.6 1920.25    5128 1924.99  5142.6 1930.13
  5157.2 1940.57  5163.5 1942.36  5170.8 1957.73  5171.8 1959.84    5178 1962.32
  5207.2  1968.8  5221.8 1973.31  5236.4 1975.85  5246.8 1980.18  5249.9 1980.18
#Mann= 4 ,-1 , 0
  4776.3     .07       0  4975.1     .05       0  4979.9     .07       0
  5170.8      .1       0
Bank Sta=4975.1,4979.9
XS Rating Curve= 0 ,0
Exp/Cntr=0.3,0.1

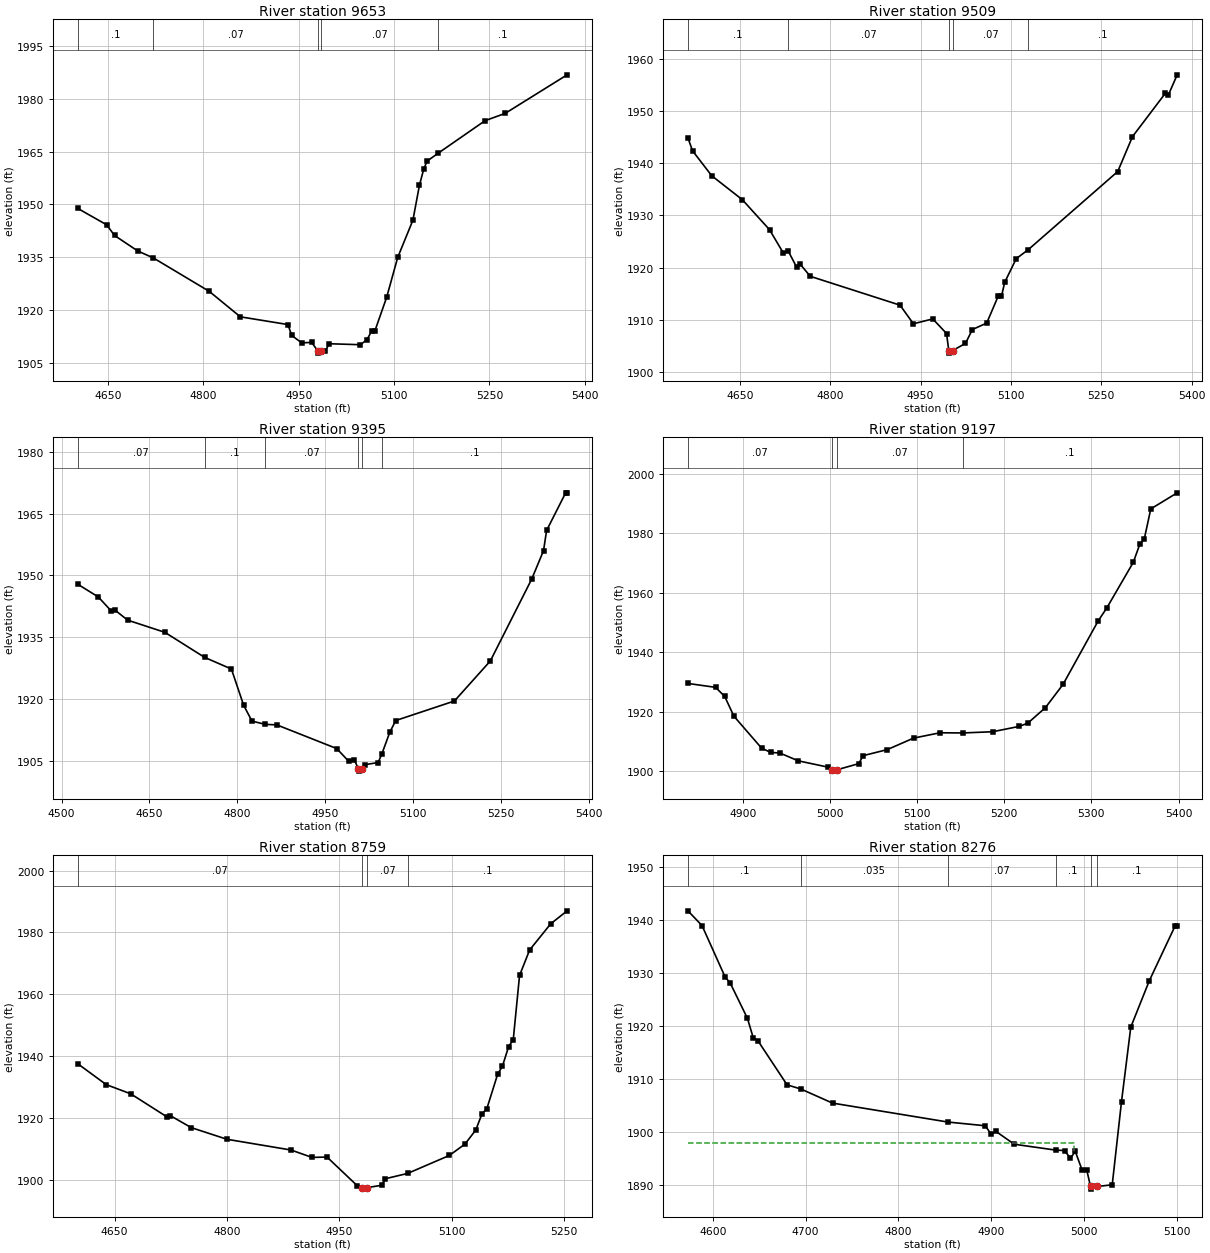
Type RM Length L Ch R = 1 ,9653    ,144,144,144
BEGIN DESCRIPTION:
Stream0198 19.0
END DESCRIPTION:
XS GIS Cut Line= 3
      1835775.01     13926524.99        1836125.       13926325.
      1836035.05     13925969.92
#Sta/Elev= 30
  4602.8 1948.83  4648.1 1944.18  4660.4 1941.16  4697.1 1936.73  4721.4 1934.78
  4809.4 1925.27  4858.3 1918.03  4933.2 1915.83    4939 1912.75  4954.8 1910.63
  4970.6 1910.76  4980.5 1908.21  4980.8 1907.71  4985.3 1908.21  4992.2 1908.41
    4998 1910.38  5047.2  1910.1  5057.5 1911.56  5064.8 1913.96    5070 1914.08
  5088.4 1923.58  5105.8 1934.93  5129.7 1945.51    5140 1955.48  5146.8 1960.08
    5152 1962.29  5169.4 1964.54  5243.2 1973.79  5274.9 1975.87  5372.2 1986.82
#Mann= 5 ,-1 , 0
  4602.8      .1       0  4721.4     .07       0  4980.5     .05       0
  4985.3     .07       0  5169.4      .1       0
Bank Sta=4980.5,4985.3
XS Rating Curve= 0 ,0
Exp/Cntr=0.3,0.1

Type RM Length L Ch R = 1 ,9509    ,114,114,114
BEGIN DESCRIPTION:
Stream0198 18.2
END DESCRIPTION:
XS GIS Cut Line= 3
      1835848.08     13926578.95       1836220.3     13926398.81
      1836591.79      13926254.1
#Sta/Elev= 30
  4563.8 1944.83  4571.5 1942.36  4603.3 1937.59    4654 1933.01  4699.2 1927.26
  4721.8 1922.85  4730.2 1923.18  4744.4 1920.04  4749.9 1920.68  4766.9 1918.32
  4915.9 1912.79  4938.1 1909.22  4970.2 1910.16  4993.1 1907.36  4996.8  1904.1
  4997.3  1903.6  5003.3  1904.1  5024.5 1905.46    5036 1908.12  5059.8 1909.36
  5078.9 1914.53  5084.3  1914.5  5089.7 1917.18  5108.8  1921.7  5128.9 1923.44
  5277.3  1938.4  5301.8 1945.09  5356.2 1953.37  5361.5 1953.11    5376 1956.93
#Mann= 5 ,-1 , 0
  4563.8      .1       0  4730.2     .07       0  4996.8     .05       0
  5003.3     .07       0  5128.9      .1       0
Bank Sta=4996.8,5003.3
XS Rating Curve= 0 ,0
Exp/Cntr=0.3,0.1

Type RM Length L Ch R = 1 ,9395    ,198,198,198
BEGIN DESCRIPTION:
Stream0198 18.1
END DESCRIPTION:
XS GIS Cut Line= 3
      1835930.98     13926790.78      1836190.35     13926503.88
      1836634.97     13926445.49
#Sta/Elev= 30
  4527.8 1947.82  4562.7 1944.74  4584.4  1941.4  4591.1 1941.55  4612.8 1939.11
  4676.3 1936.15  4744.2 1930.06  4789.9 1927.23  4810.8 1918.42    4825 1914.58
  4847.5 1913.79  4867.6 1913.65  4969.7  1907.9  4989.8 1904.87  4999.9 1905.17
  5006.7 1902.92  5007.2 1902.42  5013.3 1902.92  5018.1    1904  5040.3  1904.5
  5046.6 1906.55  5060.4 1911.91  5070.5 1914.72  5170.6 1919.46  5231.9 1929.19
  5302.5 1949.07  5322.7 1955.98    5328 1960.91  5360.5 1970.05    5363 1970.05
#Mann= 6 ,-1 , 0
  4527.8     .07       0  4744.2      .1       0  4847.5     .07       0
  5006.7     .05       0  5013.3     .07       0  5046.6      .1       0
Bank Sta=5006.7,5013.3
XS Rating Curve= 0 ,0
Exp/Cntr=0.3,0.1

Type RM Length L Ch R = 1 ,9197    ,438,438,438
BEGIN DESCRIPTION:
Stream0198 18.0
END DESCRIPTION:
XS GIS Cut Line= 3
      1836174.97     13926725.01        1836325.       13926675.
      1836725.04       13926625.
#Sta/Elev= 30
  4837.1 1929.56  4868.8 1928.25  4879.3 1925.19  4889.8 1918.56  4921.5 1907.83
    4932 1906.36  4942.5 1906.17  4963.6 1903.54  4997.8 1901.41    5002 1900.57
  5002.5 1900.07  5008.6 1900.57    5033 1902.58  5038.1 1905.27  5065.8 1907.31
    5096 1911.18  5126.3 1912.97  5152.3 1912.91  5186.7 1913.32    5217 1915.11
    5227  1916.2  5247.2 1921.42  5267.4 1929.22  5307.7 1950.57  5317.7 1954.99
    5348 1970.28  5355.5 1976.39  5360.6  1978.1  5368.1 1988.27  5398.4 1993.68
#Mann= 4 ,-1 , 0
  4837.1     .07       0    5002     .05       0  5008.6     .07       0
  5152.3      .1       0
Bank Sta=5002,5008.6
XS Rating Curve= 0 ,0
Exp/Cntr=0.3,0.1

Type RM Length L Ch R = 1 ,8759    ,483,483,483
BEGIN DESCRIPTION:
Stream0198 17.0
END DESCRIPTION:
XS GIS Cut Line= 3
      1836174.99       13927075.        1836575.       13927025.
      1836774.98     13926875.01
#Sta/Elev= 30
    4601  1937.5  4638.8 1930.78  4671.6 1927.79  4719.4 1920.42  4724.5 1920.73
  4752.2 1916.88    4800  1913.1  4885.7 1909.62  4913.4 1907.24  4933.6 1907.35
  4973.9 1898.09  4980.6 1897.48  4981.1 1896.98  4987.3 1897.48  5007.2 1898.25
  5011.4 1900.34  5041.1 1902.05  5096.8 1907.86  5117.7 1911.53  5132.2 1916.11
  5140.6 1921.43  5146.8 1922.89  5161.4 1934.17  5167.7 1936.69    5176 1943.06
  5182.2 1945.31  5190.6 1966.08  5204.1 1974.33  5232.2 1982.77  5254.1 1986.97
#Mann= 4 ,-1 , 0
    4601     .07       0  4980.6     .05       0  4987.3     .07       0
  5041.1      .1       0
Bank Sta=4980.6,4987.3
XS Rating Curve= 0 ,0
Exp/Cntr=0.3,0.1

Type RM Length L Ch R = 1 ,8276    ,445,445,445
BEGIN DESCRIPTION:
Stream0198 16.0
END DESCRIPTION:
XS GIS Cut Line= 3
      1836174.98     13927625.01        1836575.       13927475.
      1836674.98       13927475.
#Sta/Elev= 30
  4573.2  1941.8  4588.4    1939  4613.3 1929.28  4618.6 1928.21  4637.3 1921.49
  4643.5 1917.86  4648.9 1917.18    4680 1908.93  4694.9 1908.14    4729 1905.48
  4853.4  1901.9  4893.6  1901.2  4899.9  1899.6  4905.2 1900.12  4924.8 1897.71
  4969.6  1896.6  4979.1 1896.52  4985.3 1895.05  4990.6 1896.35  4997.8  1892.9
  5002.9  1892.9    5007 1889.73  5007.5 1889.23  5013.8 1889.73  5030.4 1890.04
  5040.4 1905.76  5050.4 1919.83  5070.4 1928.61  5097.9 1938.85  5100.4 1938.85
#Mann= 6 ,-1 , 0
  4573.2      .1       0  4694.9    .035       0  4853.4     .07       0
  4969.6      .1       0    5007     .05       0  5013.8      .1       0
#XS Ineff= 2 , 0
         4989.28 1898.01
Permanent Ineff=
       F       F
Bank Sta=5007,5013.8
XS Rating Curve= 0 ,0
Exp/Cntr=0.3,0.1

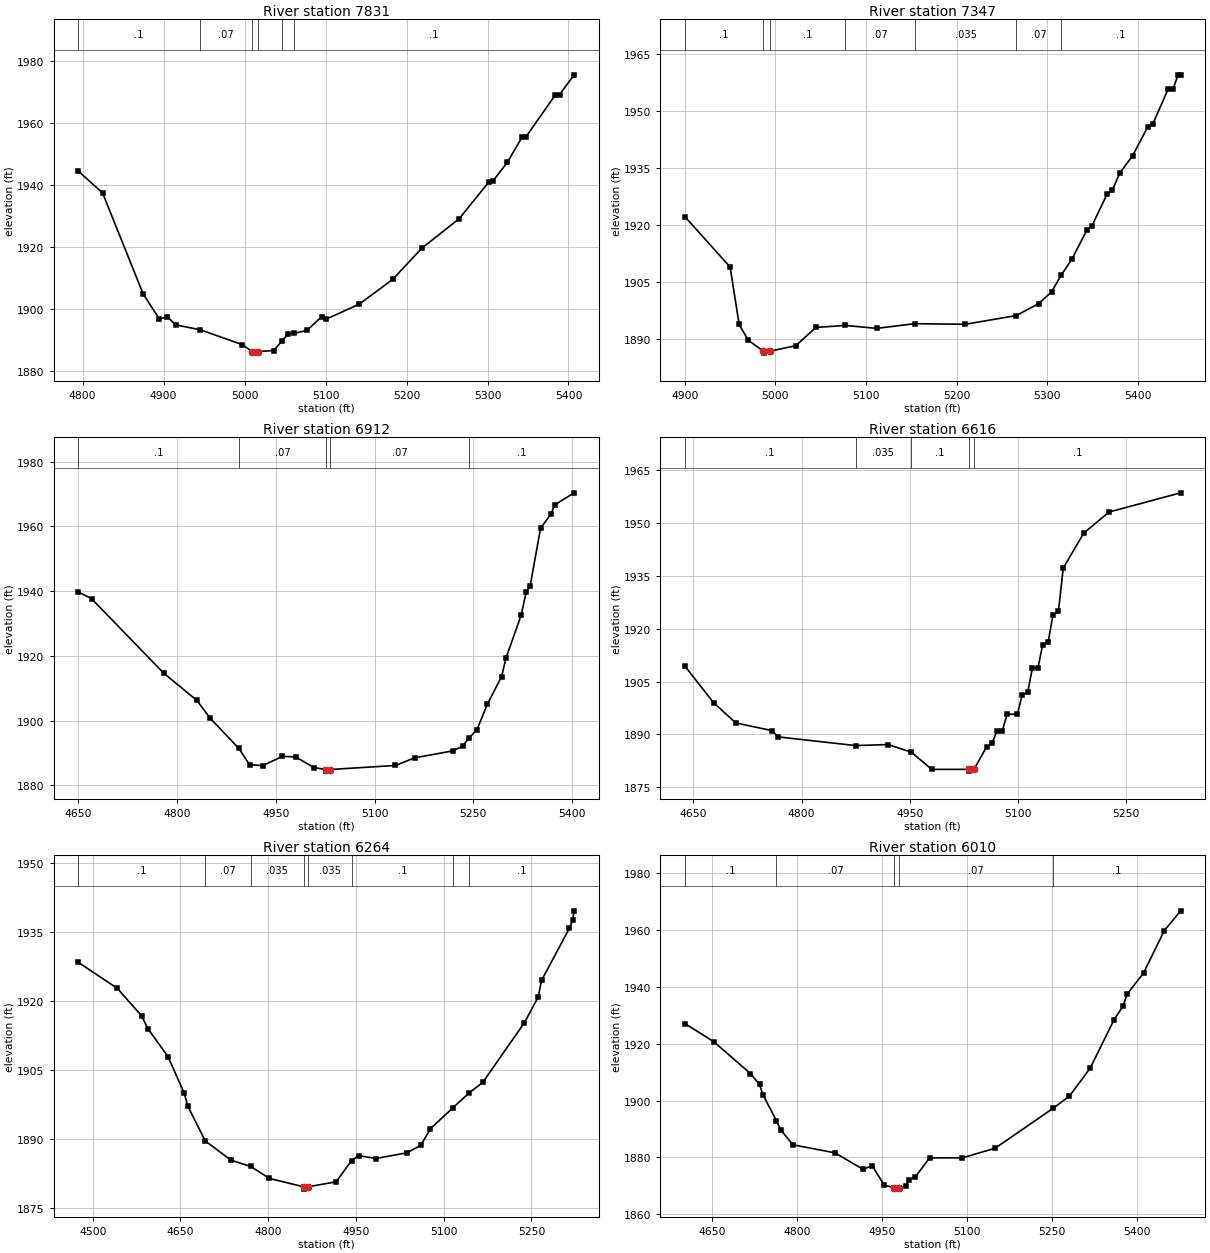
Type RM Length L Ch R = 1 ,7831    ,484,484,484
BEGIN DESCRIPTION:
Stream0198 15.0
END DESCRIPTION:
XS GIS Cut Line= 3
      1836225.05       13927875.        1836425.       13927875.
      1836825.04     13927774.99
#Sta/Elev= 30
  4794.7 1944.56  4824.7 1937.47  4874.7  1904.9  4894.7  1896.8  4904.7 1897.48
  4914.7 1894.89    4945 1893.31  4997.2  1888.5  5009.3 1886.25  5009.8 1885.75
  5016.1 1886.25  5035.9 1886.58  5045.6 1889.51  5053.9 1892.01  5061.3 1892.15
  5077.1 1893.09  5095.2 1897.55  5100.3 1896.68  5141.5 1901.56  5182.8 1909.54
  5218.8 1919.63  5265.2 1929.21  5301.3 1940.94  5306.5 1941.28  5324.5 1947.41
  5342.5 1955.45  5347.7 1955.73  5383.8 1969.17  5388.9 1969.28    5407 1975.66
#Mann= 6 ,-1 , 0
  4794.7      .1       0    4945     .07       0  5009.3     .05       0
  5016.1     .07       0  5045.6    .035       0  5061.3      .1       0
Bank Sta=5009.3,5016.1
XS Rating Curve= 0 ,0
Exp/Cntr=0.3,0.1

Type RM Length L Ch R = 1 ,7347    ,435,435,435
BEGIN DESCRIPTION:
Stream0198 14.0
END DESCRIPTION:
XS GIS Cut Line= 3
      1836324.99       13928325.        1836425.       13928325.
      1836824.98     13928125.01
#Sta/Elev= 30
    4900 1922.22    4950 1908.95    4960 1893.84    4970 1889.71  4986.6 1886.81
  4987.1 1886.31  4993.5 1886.81  5022.4 1888.26  5044.7 1893.07  5077.3 1893.59
  5111.8 1892.82  5153.7 1894.05  5209.6  1893.9  5265.8 1896.19  5290.7 1899.35
  5304.7  1902.4  5315.5 1906.86    5327 1910.94  5343.8 1918.68  5349.4 1919.83
  5366.2 1928.21  5371.8 1929.19  5380.1 1933.66  5394.1  1938.2  5410.9 1945.78
  5416.5  1946.6  5433.3 1955.68  5438.8 1955.76  5444.4  1959.5  5447.2  1959.5
#Mann= 7 ,-1 , 0
    4900      .1       0  4986.6     .05       0  4993.5      .1       0
  5077.3     .07       0  5153.7    .035       0  5265.8     .07       0
  5315.5      .1       0
Bank Sta=4986.6,4993.5
XS Rating Curve= 0 ,0
Exp/Cntr=0.3,0.1

Type RM Length L Ch R = 1 ,6912    ,296,296,296
BEGIN DESCRIPTION:
Stream0198 13.0
END DESCRIPTION:
XS GIS Cut Line= 3
      1836225.03       13928675.        1836575.       13928675.
      1836925.01     13928474.99
#Sta/Elev= 30
  4650.1 1939.73  4670.1 1937.67  4780.1 1914.57  4830.1 1906.24  4850.1 1900.77
    4894 1891.36  4910.1 1886.35  4930.1 1886.05  4960.1 1888.92  4980.1 1888.74
    5008 1885.45  5026.1 1884.85  5026.6 1884.35    5033 1884.85  5131.8 1886.11
  5161.3 1888.47  5218.9 1890.61    5234 1892.09  5242.8 1894.44  5255.6 1897.18
  5271.5  1905.1    5293 1913.58  5299.5  1919.2  5322.6 1932.52  5330.5 1939.85
  5336.2 1941.43  5352.1 1959.41  5367.9 1963.85  5373.7 1966.67  5403.2 1970.39
#Mann= 5 ,-1 , 0
  4650.1      .1       0    4894     .07       0  5026.1     .05       0
    5033     .07       0  5242.8      .1       0
Bank Sta=5026.1,5033
XS Rating Curve= 0 ,0
Exp/Cntr=0.3,0.1

Type RM Length L Ch R = 1 ,6616    ,352,352,352
BEGIN DESCRIPTION:
Stream0198 12.0
END DESCRIPTION:
XS GIS Cut Line= 3
      1836424.95     13928925.01      1836784.65     13928884.14
       1836998.4     13928639.07
#Sta/Elev= 30
    4638  1909.4  4677.8 1899.04  4708.5 1893.29  4758.8 1891.09  4767.4 1889.32
  4874.6 1886.86  4919.8 1887.15    4952 1884.98  4980.2 1880.12  5031.9 1880.12
  5032.4 1879.62  5038.8 1880.12  5056.2 1886.47  5063.8 1887.45  5070.4 1890.95
    5078 1890.95  5084.7 1895.76  5098.9 1895.71  5105.5 1901.07  5113.2  1901.9
  5119.8 1908.92  5127.4  1908.8    5134 1915.39  5141.6 1916.17  5148.3 1923.87
  5155.9 1924.92  5162.5 1937.14    5191 1947.08  5226.1 1953.03  5325.2 1958.46
#Mann= 5 ,-1 , 0
    4638      .1       0  4874.6    .035       0    4952      .1       0
  5031.9     .05       0  5038.8      .1       0
Bank Sta=5031.9,5038.8
XS Rating Curve= 0 ,0
Exp/Cntr=0.3,0.1

Type RM Length L Ch R = 1 ,6264    ,254,254,254
BEGIN DESCRIPTION:
Stream0198 11.1
END DESCRIPTION:
XS GIS Cut Line= 3
      1836250.65     13929049.13      1836707.27     13929177.19
      1837051.69     13929321.35
#Sta/Elev= 30
  4475.4 1928.38  4542.2 1922.72  4583.8 1916.73  4594.5 1913.95  4628.6 1907.93
  4656.5 1899.96  4662.7 1897.13  4692.3 1889.62  4736.1 1885.44    4770 1884.07
  4801.9 1881.47  4860.5 1879.64    4861 1879.14  4867.8 1879.64  4916.1 1880.73
  4942.4 1885.33  4954.8 1886.41    4984 1885.79    5037 1887.02  5060.8 1888.64
  5077.3 1892.24  5116.1 1896.85    5143 1899.98  5166.8 1902.32  5238.1  1915.3
  5261.5 1920.85  5267.3 1924.48  5314.9 1935.79  5320.3 1937.52    5323 1939.57
#Mann= 8 ,-1 , 0
  4475.4      .1       0  4692.3     .07       0    4770    .035       0
  4860.5     .05       0  4867.8    .035       0  4942.4      .1       0
  5116.1     .07       0    5143      .1       0
Bank Sta=4860.5,4867.8
XS Rating Curve= 0 ,0
Exp/Cntr=0.3,0.1

Type RM Length L Ch R = 1 ,6010    ,561,561,561
BEGIN DESCRIPTION:
Stream0198 11.0
END DESCRIPTION:
XS GIS Cut Line= 3
      1836224.98     13929174.99        1836575.       13929375.
      1836974.97     13929624.98
#Sta/Elev= 30
  4602.1 1927.09  4653.2 1920.72    4718 1909.48  4733.9 1905.68  4740.3 1901.91
  4763.8 1892.93  4771.3 1889.67  4792.9 1884.44    4867 1881.61  4916.7 1875.81
  4932.5 1877.13  4954.1 1870.23    4972 1869.35  4972.5 1868.85  4979.4 1869.35
  4991.6 1869.79  4997.3 1872.18  5008.2 1872.98  5034.1 1879.85  5091.9 1879.86
  5149.7 1883.24  5251.6 1897.23  5280.6 1901.55  5317.2 1911.35  5359.6 1928.49
  5374.9 1933.09  5382.6 1937.48  5411.5 1944.89    5448 1959.71  5476.9 1966.73
#Mann= 5 ,-1 , 0
  4602.1      .1       0  4763.8     .07       0    4972     .05       0
  4979.4     .07       0  5251.6      .1       0
Bank Sta=4972,4979.4
XS Rating Curve= 0 ,0
Exp/Cntr=0.3,0.1

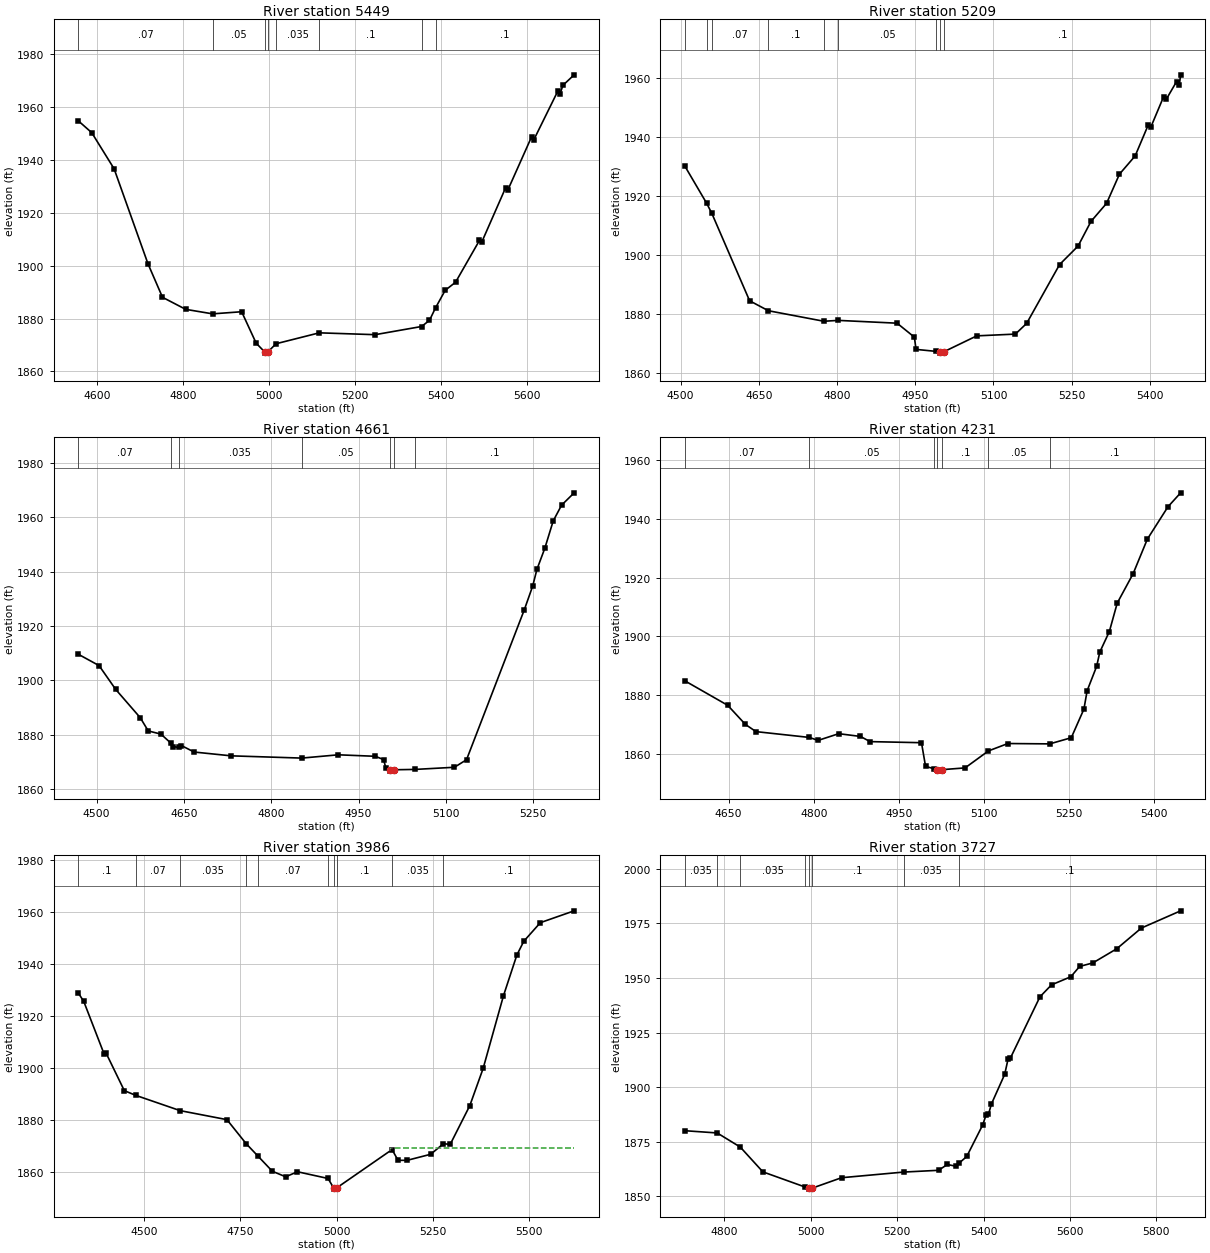
Type RM Length L Ch R = 1 ,5449    ,240,240,240
BEGIN DESCRIPTION:
Stream0198 10.0
END DESCRIPTION:
XS GIS Cut Line= 3
        1835875.       13929875.      1836309.16     13929750.12
      1837000.75     13929634.19
#Sta/Elev= 30
    4556  1954.7  4587.2 1950.23  4639.2 1936.58    4718 1900.67  4751.7 1888.03
  4805.7 1883.47  4868.3 1881.77  4935.8 1882.57  4969.5  1870.7    4989 1867.43
  4989.5 1866.93    4997 1867.43  5015.8 1870.48  5116.3  1874.6  5246.1  1873.9
  5354.1 1876.99  5372.5  1879.3  5386.6 1884.02  5409.1 1890.66  5433.2 1893.72
  5488.8 1909.52  5493.9  1908.8  5549.5 1929.38  5554.5 1928.46  5610.1  1948.7
  5615.2 1947.54  5670.8 1965.88  5675.8 1964.73  5682.9 1968.13    5709 1972.09
#Mann= 8 ,-1 , 0
    4556     .07       0  4868.3     .05       0    4989     .05       0
    4997     .05       0  5015.8    .035       0  5116.3      .1       0
  5354.1     .07       0  5386.6      .1       0
Bank Sta=4989,4997
XS Rating Curve= 0 ,0
Exp/Cntr=0.3,0.1

Type RM Length L Ch R = 1 ,5209    ,548,548,548
BEGIN DESCRIPTION:
Stream0198 9.0
END DESCRIPTION:
XS GIS Cut Line= 4
      1836062.25     13930012.64      1836475.26     13929860.13
      1836522.08     13929818.84      1836940.74     13929658.53
#Sta/Elev= 30
    4508 1930.09  4549.8 1917.48  4559.9    1914  4632.3 1884.35  4668.3 1880.97
  4774.7  1877.4  4802.5 1877.69  4915.2 1876.74  4948.3 1872.01  4951.5 1867.85
  4990.7 1867.16  4997.3 1867.08  4997.8 1866.58  5005.3 1867.08    5068 1872.44
  5142.1 1873.04  5163.7 1876.68  5226.9 1896.66  5262.3 1902.92    5287 1911.27
    5317 1917.43  5341.7 1927.33  5371.8 1933.52  5396.5 1943.87  5401.8 1943.27
  5426.5 1953.67  5431.9 1952.87  5451.2 1958.74  5456.5  1957.6    5459 1961.04
#Mann= 9 ,-1 , 0
    4508     .07       0  4549.8      .1       0  4559.9     .07       0
  4668.3      .1       0  4774.7    .035       0  4802.5     .05       0
  4990.7      .1       0  4997.3     .05       0  5005.3      .1       0
Bank Sta=4997.3,5005.3
XS Rating Curve= 0 ,0
Exp/Cntr=0.3,0.1

Type RM Length L Ch R = 1 ,4661    ,430,430,430
BEGIN DESCRIPTION:
Stream0198 8.0
END DESCRIPTION:
XS GIS Cut Line= 3
      1836474.98     13930525.02        1836875.       13930175.
        1837075.       13929925.
#Sta/Elev= 30
  4468.7  1909.6  4504.3 1905.43  4532.8 1896.68    4575 1886.26  4588.8 1881.37
  4610.6  1880.2  4627.6 1876.89  4631.5 1875.62  4641.3 1875.28  4645.7 1875.99
  4667.6  1873.6  4731.2  1872.2  4852.4 1871.37  4915.3 1872.58  4978.9 1872.03
  4993.1 1870.81  4996.9 1867.74  5003.4 1867.07  5003.9 1866.57  5011.5 1867.07
  5047.3  1867.2  5114.7 1867.99  5135.5 1870.76  5234.8    1926  5249.2 1934.73
  5256.4 1940.82    5270 1948.63  5284.4 1958.69  5298.8  1964.5  5320.4 1969.04
#Mann= 7 ,-1 , 0
  4468.7     .07       0  4627.6      .1       0  4641.3    .035       0
  4852.4     .05       0  5003.4     .05       0  5011.5     .05       0
  5047.3      .1       0
Bank Sta=5003.4,5011.5
XS Rating Curve= 0 ,0
Exp/Cntr=0.3,0.1

Type RM Length L Ch R = 1 ,4231    ,245,245,245
BEGIN DESCRIPTION:
Stream0198 7.0
END DESCRIPTION:
XS GIS Cut Line= 3
      1836674.97     13930675.01        1837075.       13930525.
      1837274.98     13930125.04
#Sta/Elev= 30
  4572.7 1884.86  4648.4 1876.52  4679.5 1870.03  4698.2 1867.57  4792.5 1865.59
  4807.7 1864.58  4844.2 1866.87  4882.5 1865.93  4899.4 1864.17  4990.1  1863.8
  4997.3 1855.73  5012.6 1854.95  5018.1 1854.63  5018.6 1854.13  5026.5 1854.63
    5067 1855.23  5108.1    1861  5142.5 1863.52  5216.3  1863.4  5254.3  1865.5
  5276.6 1875.26  5282.2 1881.47    5299 1889.78  5304.6 1894.65  5321.4 1901.61
  5335.3  1911.3  5363.3 1921.28  5388.4 1933.05  5424.8 1944.07  5447.1 1948.81
#Mann= 7 ,-1 , 0
  4572.7     .07       0  4792.5     .05       0  5012.6      .1       0
  5018.1     .05       0  5026.5      .1       0  5108.1     .05       0
  5216.3      .1       0
Bank Sta=5018.1,5026.5
XS Rating Curve= 0 ,0
Exp/Cntr=0.3,0.1

Type RM Length L Ch R = 1 ,3986    ,259,259,259
BEGIN DESCRIPTION:
Stream0198 6.1
END DESCRIPTION:
XS GIS Cut Line= 2
      1836415.69     13930892.47      1837681.28     13930656.52
#Sta/Elev= 30
  4329.3  1928.8  4343.3 1925.62    4396 1905.46  4401.1 1905.81  4448.7  1891.3
  4478.6 1889.48  4593.7 1883.62  4715.1 1880.16  4764.8 1870.97  4795.5 1866.18
    4833 1860.33  4867.7  1858.2  4898.2 1860.14  4977.7 1857.55    4992 1853.96
  4992.5 1853.46  5000.4 1853.96  5143.9 1868.66  5159.4 1864.52  5183.1 1864.53
  5244.1 1866.85  5277.1 1870.89    5295 1870.69  5345.8 1885.56  5380.4 1899.86
  5433.2 1927.79  5467.9  1943.4  5485.9  1948.7  5528.9 1955.85  5616.7  1960.4
#Mann= 10 ,-1 , 0
  4329.3      .1       0  4478.6     .07       0  4593.7    .035       0
  4764.8     .05       0  4795.5     .07       0  4977.7      .1       0
    4992     .05       0  5000.4      .1       0  5143.9    .035       0
  5277.1      .1       0
#XS Ineff= 2 , 0
                          5138.5         1869.19
Permanent Ineff=
       F       F
Bank Sta=4992,5000.4
XS Rating Curve= 0 ,0
Exp/Cntr=0.3,0.1

Type RM Length L Ch R = 1 ,3727    ,435,435,435
BEGIN DESCRIPTION:
Stream0198 6.0
END DESCRIPTION:
XS GIS Cut Line= 3
      1836734.32     13931026.74      1836999.65      13931017.7
      1837864.01     13930840.11
#Sta/Elev= 30
  4708.3 1880.11  4783.3 1879.08  4836.7 1872.62  4889.1 1861.26  4987.1  1854.3
  4995.5 1853.86    4996 1853.36  5003.9 1853.86  5071.1 1858.58  5214.8 1861.17
  5295.7 1861.98  5316.1 1864.64  5336.6 1863.82  5343.3 1865.26    5361  1868.3
  5397.8 1882.69  5406.2 1887.52  5411.3 1887.59  5418.2 1892.36  5448.9 1905.92
  5456.6 1912.83  5461.7  1913.2  5530.5 1941.41  5557.3  1946.9    5602  1950.6
  5622.4 1955.33    5653 1956.94  5708.4 1963.43  5765.3  1972.9  5856.2 1980.79
#Mann= 8 ,-1 , 0
  4708.3    .035       0  4783.3     .07       0  4836.7    .035       0
  4987.1      .1       0  4995.5     .05       0  5003.9      .1       0
  5214.8    .035       0  5343.3      .1       0
Bank Sta=4995.5,5003.9
XS Rating Curve= 0 ,0
Exp/Cntr=0.3,0.1

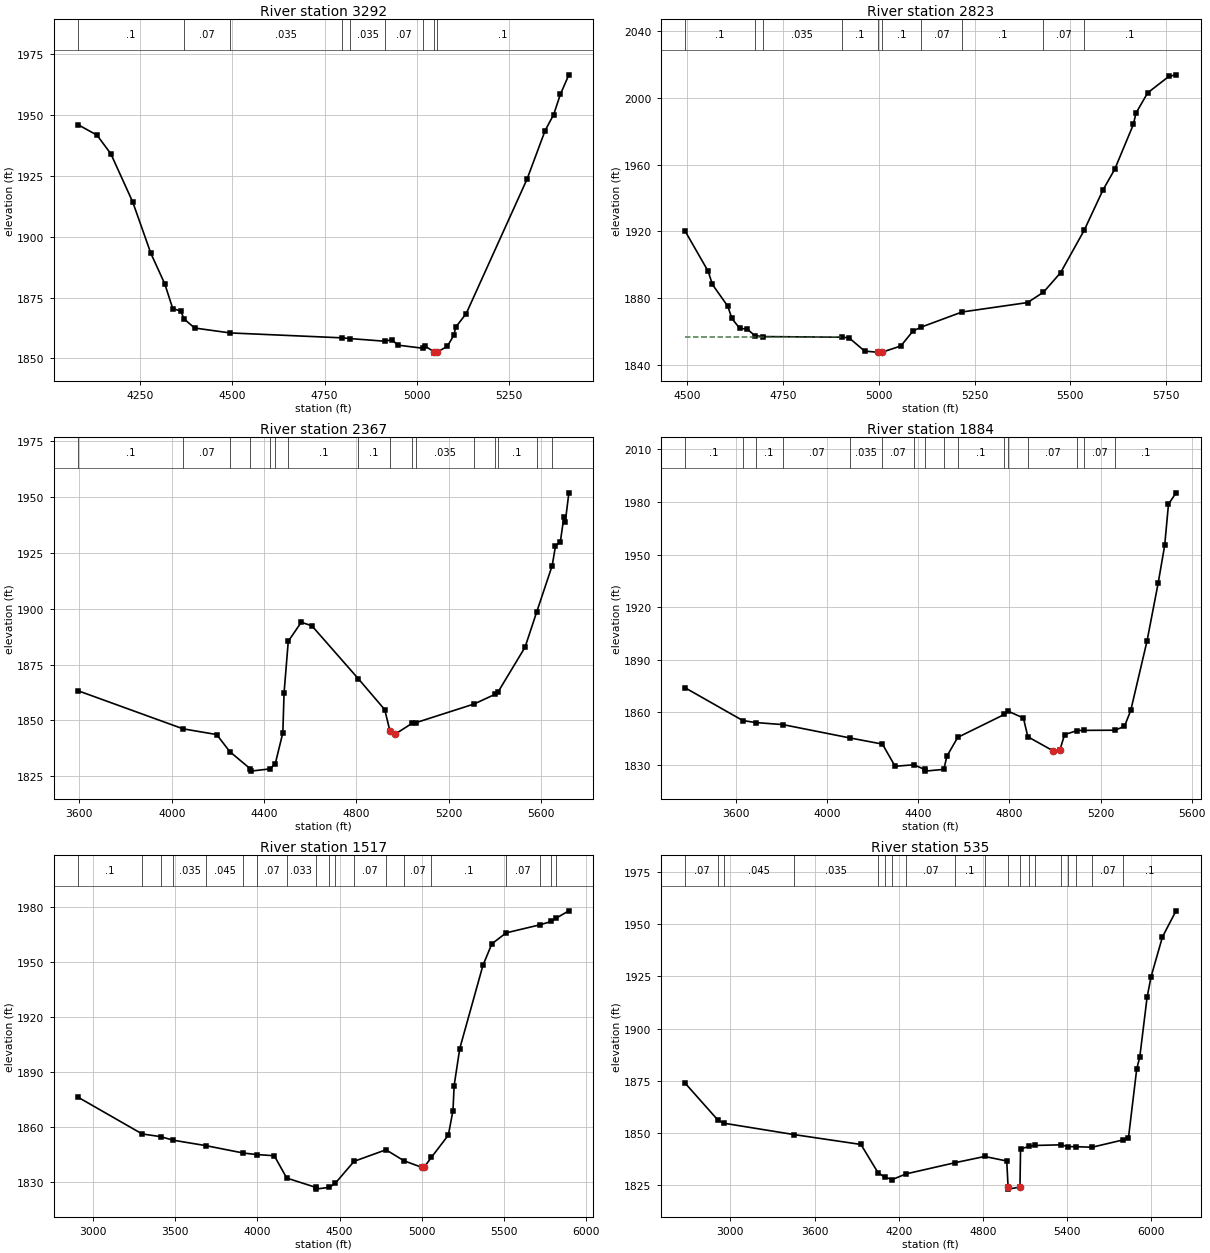
Type RM Length L Ch R = 1 ,3292    ,469,469,469
BEGIN DESCRIPTION:
Stream0198 5.0
END DESCRIPTION:
XS GIS Cut Line= 3
      1836524.99     13931775.01        1837325.       13931325.
        1837725.       13931225.
#Sta/Elev= 30
  4081.8 1946.08  4133.1 1941.79  4170.7 1934.08    4230 1914.25  4279.1 1893.15
  4316.7 1880.65  4338.4 1870.46    4360 1869.42  4369.3 1866.14  4397.7 1862.46
  4493.6 1860.44  4798.2 1858.41  4819.3 1858.11  4913.5 1857.02  4932.4 1857.68
  4948.4 1855.42  5017.7 1854.11  5022.9 1854.95    5047 1852.63  5047.5 1852.13
  5055.5 1852.63  5082.2 1854.87  5100.2 1859.44  5105.3 1862.82  5133.7 1868.38
  5298.6 1923.69  5347.6 1943.66  5370.8 1950.26  5388.8 1958.52    5412  1966.6
#Mann= 9 ,-1 , 0
  4081.8      .1       0  4369.3     .07       0  4493.6    .035       0
  4798.2      .1       0  4819.3    .035       0  4913.5     .07       0
  5017.7      .1       0    5047     .05       0  5055.5      .1       0
Bank Sta=5047,5055.5
XS Rating Curve= 0 ,0
Exp/Cntr=0.3,0.1

Type RM Length L Ch R = 1 ,2823    ,456,456,456
BEGIN DESCRIPTION:
Stream0198 4.0
END DESCRIPTION:
XS GIS Cut Line= 3
      1836735.45      13931822.6        1837225.       13931725.
      1837959.68     13931454.42
#Sta/Elev= 30
  4494.2 1920.01  4554.2 1896.02  4565.1  1888.2  4605.3 1875.16  4616.1 1867.81
  4636.5  1861.9  4656.4 1861.42  4675.8 1857.59  4696.9 1856.99  4902.7 1856.59
    4922 1856.26  4962.8 1848.28    4999 1847.57  4999.5 1847.07  5007.6 1847.57
  5057.3 1851.34  5089.3 1860.35    5111 1862.68  5217.3  1871.7  5388.5 1877.35
    5430 1883.56  5474.5 1895.16  5536.3  1920.6  5585.7  1944.9  5616.1 1957.13
  5664.8 1983.99  5671.7 1990.82  5702.2 2002.93  5757.7  2012.8  5776.3 2013.72
#Mann= 10 ,-1 , 0
  4494.2      .1       0  4675.8     .07       0  4696.9    .035       0
  4902.7      .1       0    4999     .05       0  5007.6      .1       0
    5111     .07       0  5217.3      .1       0    5430     .07       0
  5536.3      .1       0
#XS Ineff= 2 , 0
         4901.03 1856.71
Permanent Ineff=
       F       F
Bank Sta=4999,5007.6
XS Rating Curve= 0 ,0
Exp/Cntr=0.3,0.1

Type RM Length L Ch R = 1 ,2367    ,483,483,483
BEGIN DESCRIPTION:
Stream0198 3.0
END DESCRIPTION:
XS GIS Cut Line= 3
      1835898.56     13932712.98        1837175.       13932125.
      1837790.86     13931750.57
#Sta/Elev= 30
  3594.2 1863.27  4048.8 1846.24  4194.6 1843.67  4251.5 1836.02  4340.7 1828.31
  4342.2 1827.31  4425.3 1828.31  4448.4  1830.6  4481.1 1844.43  4486.6 1862.45
  4504.7  1885.4    4561 1893.92  4606.9 1892.34  4807.9 1868.68  4922.5 1854.83
  4945.4 1845.17  4967.9 1843.86  5041.3 1848.73  5059.5 1849.05  5309.6 1857.34
  5400.8 1861.69  5412.6 1862.56  5530.5 1882.77  5580.6 1898.42    5648 1919.26
  5662.2  1927.9  5683.5 1930.05    5699 1941.17  5704.9 1938.94  5720.3 1951.83
#Mann= 16 ,-1 , 0
  3594.2      .1       0  4048.8     .07       0  4251.5      .1       0
  4340.7    .035       0  4425.3      .1       0  4448.4    .033       0
  4504.7      .1       0  4807.9      .1       0  4945.4     .05       0
  5041.3      .1       0  5059.5    .035       0  5309.6     .07       0
  5400.8    .035       0  5412.6      .1       0  5580.6     .07       0
    5648      .1       0
#Block Obstruct= 2 , 0
         4575.58 1864.69
Bank Sta=4945.4,4967.9
XS Rating Curve= 0 ,0
Exp/Cntr=0.3,0.1

Type RM Length L Ch R = 1 ,1884    ,367,367,367
BEGIN DESCRIPTION:
Stream0198 2.0
END DESCRIPTION:
XS GIS Cut Line= 3
      1835902.29     13932988.71        1837425.       13932425.
      1837824.99       13932075.
#Sta/Elev= 30
  3376.3 1874.03  3628.9 1855.42    3685 1854.28  3805.2  1853.1  4100.5 1845.48
  4242.1    1842  4297.9 1829.36  4379.6 1830.21  4427.3  1827.6  4428.8  1826.6
  4511.9  1827.6  4525.1 1835.07  4572.9 1845.83  4777.2 1858.87  4792.2 1860.89
  4861.4 1856.82  4880.6 1846.19  4990.1 1838.27  5021.4 1838.66  5042.2 1847.42
  5097.3 1849.69  5126.7 1849.82  5263.3 1849.91  5305.1 1852.12  5332.7 1861.22
  5403.9 1900.62  5453.2 1933.85  5481.7 1955.22  5498.3 1978.64  5531.5 1985.14
#Mann= 16 ,-1 , 0
  3376.3      .1       0  3628.9    .035       0    3685      .1       0
  3805.2     .07       0  4100.5    .035       0  4242.1     .07       0
  4379.6    .033       0  4427.3     .05       0  4511.9    .033       0
  4572.9      .1       0  4777.2     .07       0  4792.2      .1       0
  4880.6     .07       0  5097.3    .035       0  5126.7     .07       0
  5263.3      .1       0
#Block Obstruct= 2 , 0
         4761.29 1856.35
Bank Sta=4990.1,5021.4
XS Rating Curve= 0 ,0
Exp/Cntr=0.3,0.1

Type RM Length L Ch R = 1 ,1517    ,982,982,982
BEGIN DESCRIPTION:
Stream0198 1.1
END DESCRIPTION:
XS GIS Cut Line= 4
      1835818.53     13933092.31      1837395.63     13932907.99
       1837918.5     13932385.31      1838159.99     13931770.05
#Sta/Elev= 30
  2908.4 1876.36  3298.4 1856.34  3411.1 1854.86  3487.4 1852.92  3686.2 1849.96
  3913.8 1845.93  3999.5 1845.07  4102.9 1844.45  4178.7 1832.28  4354.1 1827.24
  4355.6 1826.24  4438.7 1827.24  4474.8  1829.5    4589 1841.41  4782.9  1847.7
  4891.6 1841.75  4999.9 1838.15 5014.98 1838.16  5059.1 1843.53  5162.6 1855.66
  5190.9 1869.09  5197.9  1882.7  5232.2 1902.92  5373.3 1948.27  5427.6 1960.04
    5515 1966.01  5719.1 1970.37  5789.9 1972.21  5818.9 1974.02  5896.5 1978.02
#Mann= 19 ,-1 , 0
  2908.4      .1       0  3298.4    .035       0  3411.1     .07       0
  3487.4    .035       0  3686.2    .045       0  3913.8    .035       0
  3999.5     .07       0  4178.7    .033       0  4354.1     .05       0
  4438.7    .033       0  4474.8      .1       0    4589     .07       0
  4782.9    .035       0  4891.6     .07       0  5059.1      .1       0
    5515     .07       0  5719.1      .1       0  5789.9     .07       0
  5818.9      .1       0
#Block Obstruct= 2 , 0
         4794.19 1847.62
Bank Sta=4999.9,5014.98
XS Rating Curve= 0 ,0
Exp/Cntr=0.3,0.1

Type RM Length L Ch R = 1 ,535     ,0,0,0
BEGIN DESCRIPTION:
Stream0198 1.0
END DESCRIPTION:
XS GIS Cut Line= 4
      1836123.94     13933385.19        1838425.       13933075.
      1838753.12       13932941.      1839157.34     13932225.26
#Sta/Elev= 30
  2678.2 1873.68  2911.4 1855.98  2953.9  1854.5  3453.9 1849.04  3930.5  1844.3
    4053 1830.65  4099.1 1828.67  4152.9 1827.43  4252.8 1830.17  4599.9 1835.51
  4812.7 1838.53  4969.8 1836.35  4979.4 1823.84  4980.9 1822.84    5064 1823.84
  5068.2 1842.15  5131.5  1843.4  5170.3 1843.82    5356 1844.12  5404.9 1843.29
  5466.9 1843.23  5577.9 1842.96  5801.6 1846.53  5837.1 1847.32  5896.3 1880.57
    5918 1886.26  5970.1 1914.97  5998.8 1924.95  6079.7 1944.02  6176.5 1956.54
#Mann= 19 ,-1 , 0
  2678.2     .07       0  2911.4    .035       0  2953.9    .045       0
  3453.9    .035       0    4053      .1       0  4099.1    .033       0
  4152.9      .1       0  4252.8     .07       0  4599.9      .1       0
  4812.7      .1       0  4979.4     .05       0    5064      .1       0
  5131.5      .1       0  5170.3     .07       0    5356      .1       0
  5404.9    .035       0  5466.9      .1       0  5577.9     .07       0
  5801.6      .1       0
#Block Obstruct= 2 , 0
         4818.99 1838.27
Bank Sta=4979.4,5064
XS Rating Curve= 0 ,0
Exp/Cntr=0.3,0.1

Chan Stop Cuts=-1
Use User Specified Reach Order=0
Composite Channel Slope=5