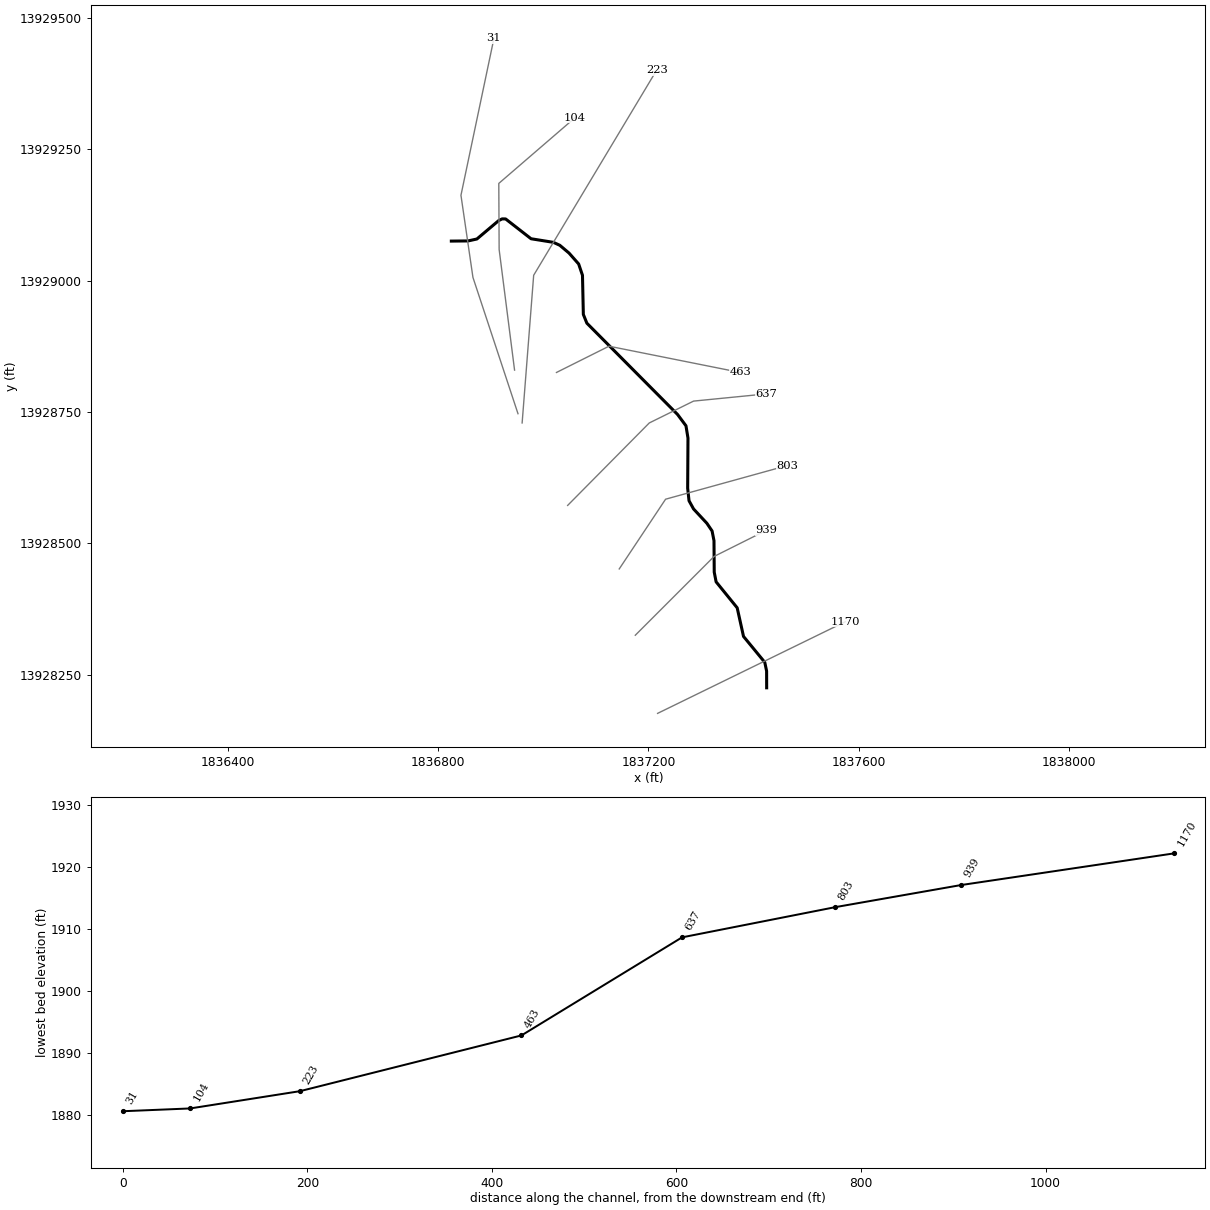
--- Stream0199.prj (project) ---

Proj Title=Stream0199 Base Level Engineering
Current Plan=p01
Default Exp/Contr=0.3,0.1
English Units
Geom File=g01
Flow File=f01
Plan File=p01
Y Axis Title=Elevation
X Axis Title(PF)=Main Channel Distance
X Axis Title(XS)=Station
BEGIN DESCRIPTION:
Stream0199
END DESCRIPTION:
DSS Export Rating Curves= 0
DSS Export Rating Curve Sorted= 0
DSS Export Volume Flow Curves= 0
DXF OffsetX= 0
DXF OffsetY= 0
DXF ScaleX= 1
DXF ScaleY= 10

--- Stream0199.p01 (plan) ---

Plan Title=Multiple Run
Short Identifier=Multiple
Geom File=g01
Flow File=f01
Subcritical Flow
K Sum by GR= 0
Std Step Tol= 0.01
Critical Tol= 0.01
Num of Std Step Trials= 20
Max Error Tol= 0.3
Flow Tol Ratio= 0.001
Split Flow NTrial= 30
Split Flow Tol= 0.02
Split Flow Ratio= 0.02
Log Output Level= 0
Friction Slope Method= 1
Unsteady Friction Slope Method= 2
Unsteady Bridges Friction Slope Method= 1
Parabolic Critical Depth
Global Vel Dist=  1 , 1 , 1
Global Log Level= 0
CheckData=True
Encroach Param= -1, 0, 0, 0
BEGIN DESCRIPTION:
Multiple Run
END DESCRIPTION:

--- Stream0199.f01 (steady flow) ---

Flow Title=Multiple
Program Version=4.10
Number of Profiles= 7
Profile Names=10-year,25-year,50-year,1pct_min,100-year,1pct_plu,500-year
River Rch & RM=Stream0199,Reach-1         ,1170
     443     724     983     649    1294    2582    2208
Boundary for River Rch & Prof#=Stream0199,Reach-1         , 1
Up Type= 0
Dn Type= 3
Dn Slope=0.02
Boundary for River Rch & Prof#=Stream0199,Reach-1         , 2
Up Type= 0
Dn Type= 3
Dn Slope=0.02
Boundary for River Rch & Prof#=Stream0199,Reach-1         , 3
Up Type= 0
Dn Type= 3
Dn Slope=0.02
Boundary for River Rch & Prof#=Stream0199,Reach-1         , 4
Up Type= 0
Dn Type= 3
Dn Slope=0.02
Boundary for River Rch & Prof#=Stream0199,Reach-1         , 5
Up Type= 0
Dn Type= 3
Dn Slope=0.02
Boundary for River Rch & Prof#=Stream0199,Reach-1         , 6
Up Type= 0
Dn Type= 3
Dn Slope=0.02
Boundary for River Rch & Prof#=Stream0199,Reach-1         , 7
Up Type= 0
Dn Type= 3
Dn Slope=0.02
DSS Import GetInterval= 0
DSS Import GetPeak= 0
DSS Import FillOption= 0

--- Stream0199.g01 (geometry) ---

Geom Title=Existing Conditions

River Reach=Stream0199,Reach-1
Reach XY= 30
      1837425.00     13928225.00      1837424.90     13928256.81
      1837421.40     13928273.51      1837380.95     13928322.75
      1837368.90     13928377.19      1837328.82     13928426.58
      1837325.23     13928445.09      1837324.76     13928504.90
      1837321.14     13928523.40      1837311.17     13928538.13
      1837285.85     13928565.35      1837277.27     13928580.94
      1837274.68     13928604.87      1837275.27     13928700.11
      1837271.46     13928723.53      1837255.39     13928745.16
      1837082.86     13928918.83      1837076.17     13928935.49
      1837074.53     13929009.91      1837067.25     13929031.46
      1837048.95     13929052.20      1837031.38     13929067.02
      1837019.15     13929072.63      1836976.68     13929079.46
      1836928.28     13929117.15      1836921.66     13929117.26
      1836915.04     13929113.97      1836873.64     13929079.00
      1836856.88     13929075.31      1836825.00     13929075.00

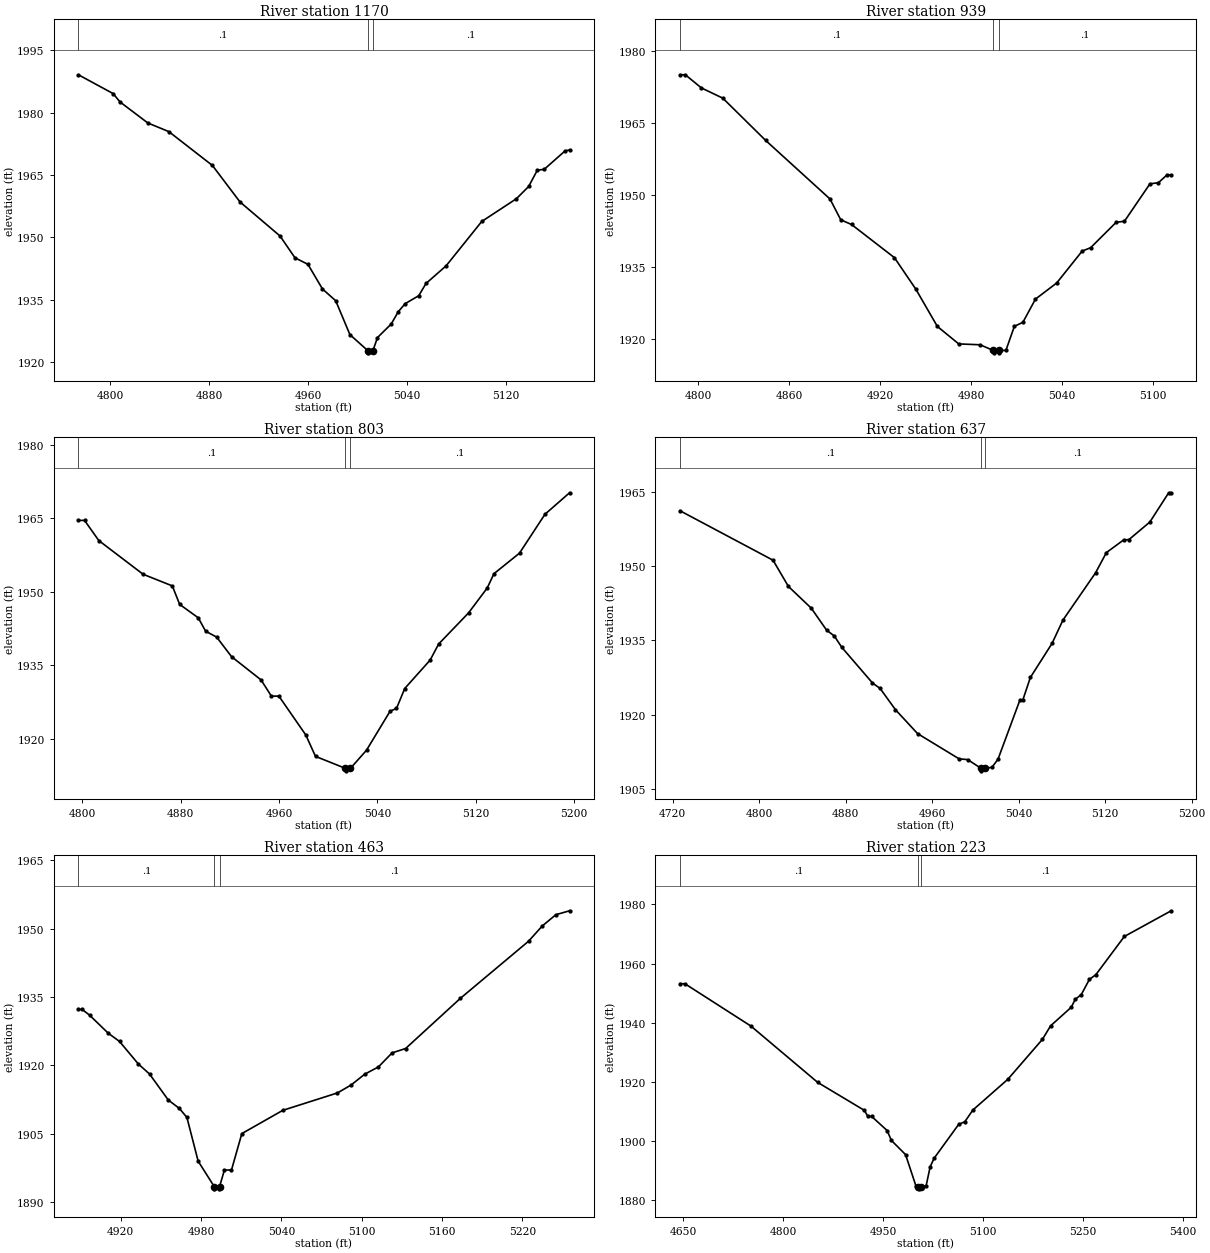
Type RM Length L Ch R = 1,1170,231,231,231
BEGIN DESCRIPTION:
Stream0199 3.0
END DESCRIPTION:
XS GIS Cut Line= 2
      1837217.47     13928176.34      1837574.75     13928350.80
#Sta/Elev= 30
  4774.2 1989.14  4802.3 1984.61  4807.9 1982.59  4830.4 1977.53  4847.4 1975.45
  4882.7 1967.29  4905.0 1958.51  4937.4 1950.31  4949.5 1945.06  4960.0 1943.48
  4971.8 1937.53  4982.5 1934.71  4994.0 1926.54  5008.6 1922.66  5008.8 1922.16
  5012.6 1922.66  5016.3 1925.84  5027.4 1929.09  5033.1 1932.05  5038.7 1934.00
  5049.7 1935.92  5055.6 1938.87  5071.9 1943.13  5100.7 1953.80  5128.8 1959.29
  5138.7 1962.23  5145.7 1966.15  5151.3 1966.37  5168.2 1970.81  5171.8 1971.03
#Mann=3,-1,0
  4774.2     0.1       0  5008.6    0.05       0  5012.6     0.1       0
Bank Sta=5008.6,5012.6
Exp/Cntr=0.3,0.1

Type RM Length L Ch R = 1,939,136,136,136
BEGIN DESCRIPTION:
Stream0199 2.0
END DESCRIPTION:
XS GIS Cut Line= 3
      1837175.03     13928325.03      1837325.00     13928475.00
      1837425.01     13928525.00
#Sta/Elev= 30
  4787.9 1974.97  4791.4 1974.97  4802.0 1972.23  4816.1 1970.10  4844.4 1961.29
  4886.8 1949.10  4893.9 1944.76  4901.0 1943.79  4929.3 1936.88  4943.4 1930.32
  4957.6 1922.56  4971.7 1918.92  4985.8 1918.74  4994.5 1917.56  4994.7 1917.06
  4998.2 1917.06  4998.5 1917.56  5002.8 1917.56  5008.4 1922.59  5014.0 1923.41
  5022.3 1928.25  5036.3 1931.61  5053.1 1938.25  5058.7 1938.96  5075.5 1944.24
  5081.0 1944.47  5097.8 1952.26  5103.4 1952.49  5109.0 1954.11  5111.8 1954.11
#Mann=3,-1,0
  4787.9     0.1       0  4994.5    0.05       0  4998.5     0.1       0
Bank Sta=4994.5,4998.5
Exp/Cntr=0.3,0.1

Type RM Length L Ch R = 1,803,166,166,166
BEGIN DESCRIPTION:
Stream0199 1.2
END DESCRIPTION:
XS GIS Cut Line= 3
      1837144.48     13928451.19      1837232.67     13928583.87
      1837464.26     13928647.92
#Sta/Elev= 30
  4796.7 1964.55  4801.7 1964.55  4813.3 1960.44  4849.3 1953.58  4873.1 1951.20
  4879.1 1947.43  4894.2 1944.70  4900.2 1941.97  4909.2 1940.76  4921.3 1936.78
  4945.3 1932.04  4953.7 1928.74  4959.8 1928.74  4981.7 1920.82  4989.6 1916.46
  5014.0 1914.01  5014.3 1913.51  5018.0 1914.01  5031.1 1917.72  5050.3 1925.67
  5055.5 1926.23  5062.2 1930.29  5082.9 1936.09  5089.8 1939.36  5114.1 1945.69
  5129.3 1950.77  5134.8 1953.69  5155.6 1957.88  5176.3 1965.80  5196.3 1970.18
#Mann=3,-1,0
  4796.7     0.1       0  5014.0    0.05       0  5018.0     0.1       0
Bank Sta=5014,5018
Exp/Cntr=0.3,0.1

Type RM Length L Ch R = 1,637,174,174,174
BEGIN DESCRIPTION:
Stream0199 1.1
END DESCRIPTION:
XS GIS Cut Line= 4
      1837046.31     13928572.05      1837201.58     13928728.92
      1837285.89     13928770.54      1837424.57     13928784.26
#Sta/Elev= 30
  4726.9 1961.13  4812.9 1951.15  4827.1 1945.86  4848.3 1941.46  4862.4 1937.04
  4869.5 1935.87  4876.5 1933.56  4904.8 1926.39  4911.9 1925.27  4926.1 1920.98
  4946.5 1916.17  4984.9 1911.07  4992.9 1910.92  5005.2 1909.15  5005.4 1908.65
  5009.2 1909.15  5015.3 1909.36  5020.9 1911.00  5041.0 1922.85  5043.7 1922.85
  5050.8 1927.49  5070.9 1934.38  5080.9 1939.06  5111.1 1948.61  5121.1 1952.69
  5137.0 1955.24  5142.0 1955.32  5161.3 1958.86  5178.7 1964.76  5181.0 1964.76
#Mann=3,-1,0
  4726.9     0.1       0  5005.2    0.05       0  5009.2     0.1       0
Bank Sta=5005.2,5009.2
Exp/Cntr=0.3,0.1

Type RM Length L Ch R = 1,463,240,240,240
BEGIN DESCRIPTION:
Stream0199 1.0
END DESCRIPTION:
XS GIS Cut Line= 3
      1837025.03     13928825.01      1837125.00     13928875.00
      1837374.98     13928825.00
#Sta/Elev= 30
  4888.5 1932.25  4891.3 1932.25  4896.9 1930.97  4910.8 1927.02  4919.2 1925.22
  4933.2 1920.29  4941.6 1918.07  4955.6 1912.37  4963.9 1910.51  4969.5 1908.55
  4977.9 1898.95  4989.9 1893.37  4990.1 1892.87  4993.6 1892.87  4993.9 1893.37
  4997.5 1897.00  5002.8 1897.00  5010.5 1904.99  5041.1 1910.10  5081.9 1913.92
  5092.1 1915.66  5102.3 1918.04  5112.5 1919.63  5122.7 1922.71  5132.8 1923.67
  5173.6 1934.66  5224.6 1947.22  5234.8 1950.56  5245.0 1953.04  5255.2 1953.90
#Mann=3,-1,0
  4888.5     0.1       0  4989.9    0.05       0  4993.9     0.1       0
Bank Sta=4989.9,4993.9
Exp/Cntr=0.3,0.1

Type RM Length L Ch R = 1,223,119,119,119
BEGIN DESCRIPTION:
Stream0199 0.0
END DESCRIPTION:
XS GIS Cut Line= 3
      1836959.70     13928728.96      1836981.66     13929010.00
      1837215.91     13929400.66
#Sta/Elev= 30
  4645.1 1953.23  4652.5 1953.20  4751.5 1938.91  4851.8 1919.87  4922.0 1910.40
  4927.0 1908.37  4932.8 1908.37  4956.1 1903.59  4962.3 1900.29  4983.7 1895.47
  4999.2 1884.93  5003.1 1884.40  5003.3 1883.90  5007.1 1884.40  5014.4 1884.74
  5020.6 1891.32  5026.5 1894.21  5063.4 1905.67  5072.7 1906.59  5084.8 1910.54
  5137.3 1920.93  5189.3 1934.45  5201.4 1938.97  5232.5 1945.27  5238.4 1947.92
  5247.6 1949.56  5259.7 1954.67  5269.5 1956.30  5312.2 1969.19  5382.5 1977.87
#Mann=3,-1,0
  4645.1     0.1       0  5003.1    0.05       0  5007.1     0.1       0
Bank Sta=5003.1,5007.1
Exp/Cntr=0.3,0.1

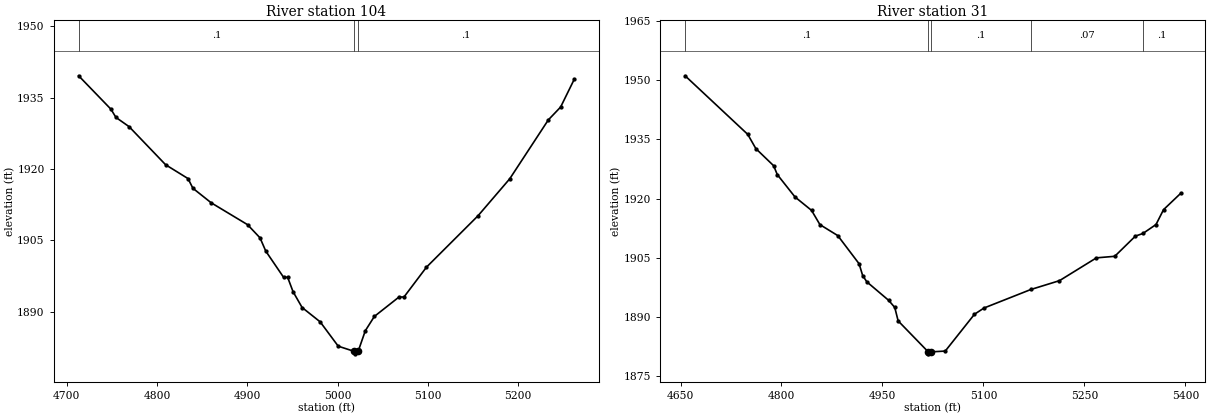
Type RM Length L Ch R = 1,104,73,73,73
BEGIN DESCRIPTION:
Stream0199 0.1
END DESCRIPTION:
XS GIS Cut Line= 4
      1836945.30     13928829.50      1836915.95     13929059.06
      1836915.30     13929184.76      1837060.33     13929309.77
#Sta/Elev= 30
  4713.3 1939.63  4749.1 1932.59  4754.6 1930.87  4769.2 1928.92  4809.6 1920.91
  4834.4 1918.00  4839.8 1915.96  4860.0 1912.91  4900.3 1908.30  4914.1 1905.53
  4920.5 1902.73  4940.2 1897.22  4944.7 1897.22  4950.7 1894.19  4960.7 1890.87
  4980.7 1887.85  5000.7 1882.73  5018.7 1881.62  5018.9 1881.12  5022.7 1881.62
  5030.7 1885.99  5040.7 1888.99  5068.0 1893.08  5073.5 1893.08  5098.4 1899.36
  5155.4 1910.16  5190.6 1917.96  5233.3 1930.35  5246.9 1933.05  5261.9 1938.86
#Mann=3,-1,0
  4713.3     0.1       0  5018.7    0.05       0  5022.7     0.1       0
Bank Sta=5018.7,5022.7
Exp/Cntr=0.3,0.1

Type RM Length L Ch R = 1,31,0,0,0
BEGIN DESCRIPTION:
Stream0199 0.2
END DESCRIPTION:
XS GIS Cut Line= 4
      1836951.81     13928746.58      1836866.09     13929005.93
      1836843.30     13929162.18      1836906.05     13929460.81
#Sta/Elev= 30
  4656.8 1951.12  4749.9 1936.27  4761.9 1932.67  4788.4 1928.32  4793.7 1926.10
  4820.1 1920.41  4844.7 1917.01  4857.1 1913.41  4883.6 1910.63  4915.3 1903.49
  4920.6 1900.50  4926.8 1898.91  4959.3 1894.21  4968.3 1892.42  4973.3 1889.02
  5018.0 1881.17  5018.2 1880.67  5022.0 1881.17  5043.3 1881.37  5086.7 1890.70
  5101.0 1892.29  5170.6 1896.98  5213.0 1899.21  5267.9 1904.99  5295.1 1905.38
  5325.8 1910.50  5336.9 1911.16  5356.4 1913.43  5367.6 1917.20  5393.0 1921.32
#Mann=5,-1,0
  4656.8     0.1       0  5018.0    0.05       0  5022.0     0.1       0
  5170.6    0.07       0  5336.9     0.1       0
Bank Sta=5018,5022
Exp/Cntr=0.3,0.1

Chan Stop Cuts=-1