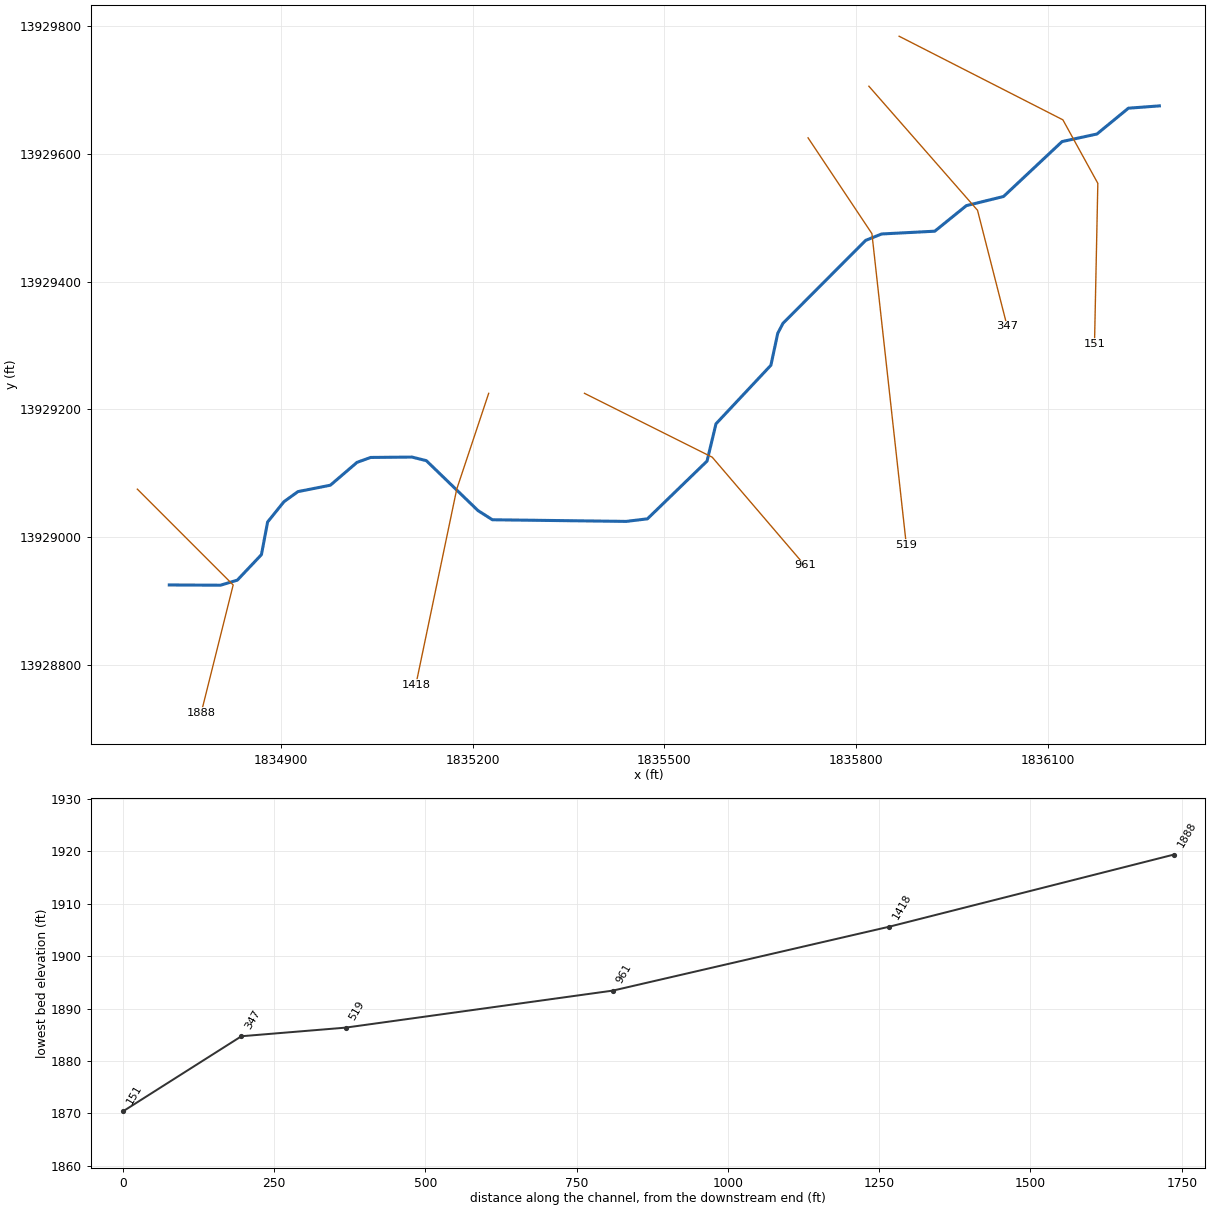
--- Stream0200.prj (project) ---

Proj Title=Stream0200 Base Level Engineering
Current Plan=p01
Default Exp/Contr=0.3,0.1
English Units
Geom File=g01
Flow File=f01
Plan File=p01
Y Axis Title=Elevation
X Axis Title(PF)=Main Channel Distance
X Axis Title(XS)=Station
BEGIN DESCRIPTION:
Stream0200
END DESCRIPTION:
DSS Export Rating Curves= 0
DSS Export Rating Curve Sorted= 0
DSS Export Volume Flow Curves= 0
DXF OffsetX= 0
DXF OffsetY= 0
DXF ScaleX= 1
DXF ScaleY= 10

--- Stream0200.p01 (plan) ---

Plan Title=Multiple Run
Short Identifier=Multiple
Geom File=g01
Flow File=f01
Subcritical Flow
K Sum by GR= 0
Std Step Tol= 0.01
Critical Tol= 0.01
Num of Std Step Trials= 20
Max Error Tol= 0.3
Flow Tol Ratio= 0.001
Split Flow NTrial= 30
Split Flow Tol= 0.02
Split Flow Ratio= 0.02
Log Output Level= 0
Friction Slope Method= 1
Unsteady Friction Slope Method= 2
Unsteady Bridges Friction Slope Method= 1
Parabolic Critical Depth
Global Vel Dist=  1 , 1 , 1
Global Log Level= 0
CheckData=True
Encroach Param= -1, 0, 0, 0
BEGIN DESCRIPTION:
Multiple Run
END DESCRIPTION:

--- Stream0200.f01 (steady flow) ---

Flow Title=Multiple
Number of Profiles=7
Profile Names=10-year,25-year,50-year,1pct_min,100-year,1pct_plu,500-year
River Rch & RM= Stream0200,Reach-1,1888
     572     952    1307     871    1738    3468    3030
Boundary for River Rch & Prof#=Stream0200,Reach-1,1
Up Type=0
Dn Type=3
Dn Slope=0.005
Boundary for River Rch & Prof#=Stream0200,Reach-1,2
Up Type=0
Dn Type=3
Dn Slope=0.005
Boundary for River Rch & Prof#=Stream0200,Reach-1,3
Up Type=0
Dn Type=3
Dn Slope=0.005
Boundary for River Rch & Prof#=Stream0200,Reach-1,4
Up Type=0
Dn Type=3
Dn Slope=0.005
Boundary for River Rch & Prof#=Stream0200,Reach-1,5
Up Type=0
Dn Type=3
Dn Slope=0.005
Boundary for River Rch & Prof#=Stream0200,Reach-1,6
Up Type=0
Dn Type=3
Dn Slope=0.005
Boundary for River Rch & Prof#=Stream0200,Reach-1,7
Up Type=0
Dn Type=3
Dn Slope=0.005

--- Stream0200.g01 (geometry) ---

Geom Title=Existing Conditions
Program Version=4.10

River Reach=Stream0200      ,Reach-1
Reach XY= 30
        1834725.       13928925.      1834805.27     13928924.62
      1834831.55      13928932.6      1834869.26     13928972.46
       1834878.9     13929023.54      1834904.53     13929055.37
      1834926.42     13929071.14      1834977.15     13929081.16
      1835018.94     13929116.96      1835040.27     13929124.64
      1835104.95     13929125.21      1835127.42     13929119.59
      1835208.25     13929041.47      1835230.86     13929027.07
      1835440.21     13929024.51      1835473.55     13929028.53
      1835566.85     13929118.93      1835580.87     13929177.28
      1835666.82     13929268.96      1835677.53     13929318.95
      1835685.78     13929334.68      1835815.21     13929464.48
      1835840.22     13929474.48      1835923.41     13929478.83
      1835972.83     13929518.86      1836031.05     13929533.16
       1836122.7     13929619.17      1836177.24     13929630.97
      1836226.49      13929671.4        1836275.       13929675.

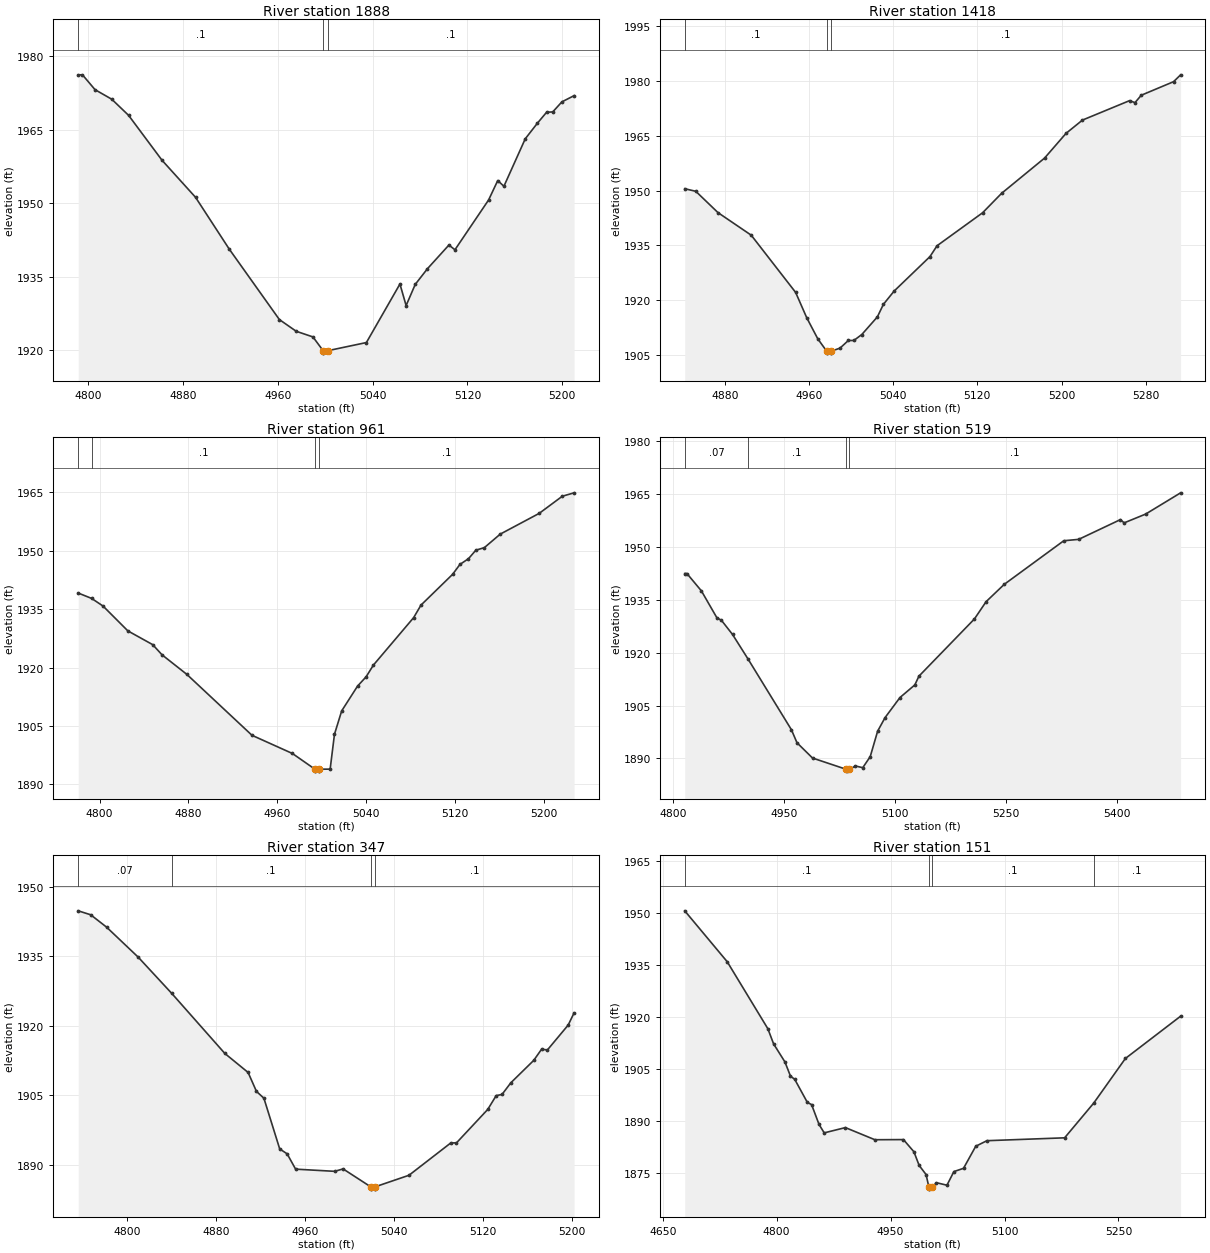
Type RM Length L Ch R = 1 ,1888    ,470,470,470
BEGIN DESCRIPTION:
Stream0200 4.0
END DESCRIPTION:
XS GIS Cut Line= 3
      1834674.97     13929075.03        1834825.       13928925.
      1834775.01     13928725.02
#Sta/Elev= 30
  4791.7 1976.19  4795.3 1976.19  4805.9 1973.16    4820 1971.21  4834.2 1967.92
  4862.4 1958.75  4890.7 1951.18    4919 1940.65  4961.4 1926.23  4975.6 1923.84
  4989.7 1922.69  4998.3 1919.88  4998.6 1919.38  5002.3 1919.88  5034.8 1921.54
  5063.1 1933.49  5068.3 1929.09    5076 1933.41  5086.3 1936.61  5104.4 1941.44
  5109.5 1940.48  5137.9 1950.65  5145.6 1954.61  5150.8 1953.44  5168.8 1963.13
  5179.1 1966.33  5186.8 1968.55    5192 1968.62  5199.7 1970.67    5210 1971.94
#Mann= 3 ,-1 , 0
  4791.7      .1       0  4998.3     .05       0  5002.3      .1       0
Bank Sta=4998.3,5002.3
XS Rating Curve= 0 ,0
Exp/Cntr=0.3,0.1

Type RM Length L Ch R = 1 ,1418    ,457,457,457
BEGIN DESCRIPTION:
Stream0200 3.0
END DESCRIPTION:
XS GIS Cut Line= 3
        1835225.       13929225.        1835175.       13929075.
      1835110.95     13928768.44
#Sta/Elev= 30
  4841.9 1950.49  4852.4 1949.79  4873.5 1943.97  4905.1 1937.81  4947.3  1922.2
  4957.9 1915.25  4968.4 1909.51  4976.9 1906.13  4977.2 1905.63  4980.7 1905.63
  4980.9 1906.13  4989.5    1907  4997.4 1909.08  5002.6 1909.08  5010.2 1910.71
    5025 1915.52  5030.7 1918.94  5040.9 1922.56    5075 1931.98  5081.7 1934.93
    5125 1943.93    5143 1949.22  5183.9 1958.85  5204.3  1965.6  5219.9 1969.22
  5264.7 1974.53  5269.8 1973.98  5275.8    1976  5306.5  1979.7  5313.2 1981.57
#Mann= 3 ,-1 , 0
  4841.9      .1       0  4976.9     .05       0  4980.9      .1       0
Bank Sta=4976.9,4980.9
XS Rating Curve= 0 ,0
Exp/Cntr=0.3,0.1

Type RM Length L Ch R = 1 ,961     ,442,442,442
BEGIN DESCRIPTION:
Stream0200 2.0
END DESCRIPTION:
XS GIS Cut Line= 3
      1835374.98     13929225.01        1835575.       13929125.
      1835719.97     13928955.59
#Sta/Elev= 30
  4780.7 1939.15  4792.8 1937.77  4803.1  1935.8  4825.4 1929.44  4847.8  1925.9
  4856.2 1923.29  4878.5 1918.28  4937.2 1902.63  4973.6 1897.96  4993.9 1893.93
  4994.2 1893.43  4997.7 1893.43  4997.9 1893.93  5007.6 1893.94  5011.5  1902.9
    5018  1908.9  5032.3 1915.27    5040 1917.65  5046.6 1920.67  5082.8 1932.84
  5089.4 1936.05  5117.9 1943.96  5124.5  1946.5  5132.2 1947.97  5138.8 1950.15
  5146.5 1950.81  5160.8 1954.28  5195.9 1959.61  5216.7 1964.01  5227.3 1964.88
#Mann= 4 ,-1 , 0
  4780.7     .07       0  4792.8      .1       0  4993.9     .05       0
  4997.9      .1       0
Bank Sta=4993.9,4997.9
XS Rating Curve= 0 ,0
Exp/Cntr=0.3,0.1

Type RM Length L Ch R = 1 ,519     ,172,172,172
BEGIN DESCRIPTION:
Stream0200 1.0
END DESCRIPTION:
XS GIS Cut Line= 3
      1835725.01     13929624.98        1835825.       13929475.
      1835878.81     13928988.02
#Sta/Elev= 30
  4815.6 1942.48  4818.6 1942.48  4838.1 1937.56  4859.1  1929.9  4865.2  1929.2
  4880.2 1925.18  4901.1 1918.22  4959.8 1898.11  4967.3 1894.42  4988.3 1890.08
  5034.1 1886.86  5034.4 1886.36  5038.1 1886.86  5046.3 1887.82  5056.2 1887.34
  5066.3 1890.48  5076.3 1897.71  5086.4 1901.58  5106.5 1907.27  5126.6 1910.85
  5132.1 1913.33  5207.1 1929.58  5222.9 1934.49  5247.4 1939.41  5327.9  1951.8
    5348 1952.19  5404.4  1957.8  5409.5 1956.88  5438.5 1959.37  5485.8 1965.41
#Mann= 4 ,-1 , 0
  4815.6     .07       0  4901.1      .1       0  5034.1     .05       0
  5038.1      .1       0
Bank Sta=5034.1,5038.1
XS Rating Curve= 0 ,0
Exp/Cntr=0.3,0.1

Type RM Length L Ch R = 1 ,347     ,196,196,196
BEGIN DESCRIPTION:
Stream0200 0.1
END DESCRIPTION:
XS GIS Cut Line= 3
      1835820.25     13929705.78       1835990.3      13929511.6
      1836036.74     13929329.85
#Sta/Elev= 30
    4756 1944.76  4767.2 1943.91  4781.5 1941.24  4809.9 1934.77  4840.1 1926.94
  4887.8 1913.99  4908.7 1909.89  4916.2 1905.81  4922.9 1904.33  4937.1  1893.4
  4943.8 1892.33  4951.4 1889.03  4986.5 1888.56  4994.1 1889.08  5018.9 1885.22
  5019.2 1884.72  5022.7 1884.72  5022.9 1885.22  5053.3 1887.71  5090.9 1894.69
    5096  1894.7  5124.1 1901.92  5131.7  1904.9  5136.9 1905.14  5144.8 1907.65
  5165.4 1912.49  5172.5 1914.91  5177.7 1914.74  5196.4 1920.12  5201.7 1922.75
#Mann= 4 ,-1 , 0
    4756     .07       0  4840.1      .1       0  5018.9     .05       0
  5022.9      .1       0
#XS Ineff= 2 , 0
         4994.17 1889.04
Permanent Ineff=
       F       F
Bank Sta=5018.9,5022.9
XS Rating Curve= 0 ,0
Exp/Cntr=0.3,0.1

Type RM Length L Ch R = 1 ,151     ,0,0,0
BEGIN DESCRIPTION:
Stream0200 0.0
END DESCRIPTION:
XS GIS Cut Line= 4
      1835867.55     13929784.04      1836123.95     13929653.17
      1836178.65     13929553.75      1836173.45     13929302.35
#Sta/Elev= 30
    4679 1950.65  4734.9 1935.97  4788.4 1916.65    4796 1912.26  4810.9 1907.06
  4818.2 1902.97  4823.8 1902.04  4840.4 1895.39    4846 1894.75  4855.8 1889.03
  4862.6  1886.6  4890.5 1888.12  4929.3 1884.62  4966.9 1884.66  4980.7 1881.15
  4987.6  1877.2  4996.7 1874.58  5000.5 1870.87  5000.7 1870.37  5004.5 1870.87
  5010.4 1872.22  5024.2  1871.5  5033.3 1875.43    5046 1876.37  5062.1 1882.74
  5076.8 1884.34  5179.1 1885.17  5217.4 1895.19  5259.1 1908.06  5331.8 1920.26
#Mann= 4 ,-1 , 0
    4679      .1       0  5000.5     .05       0  5004.5      .1       0
  5217.4      .1       0
Bank Sta=5000.5,5004.5
XS Rating Curve= 0 ,0
Exp/Cntr=0.3,0.1

Chan Stop Cuts=-1
Use User Specified Reach Order=0
Composite Channel Slope=5