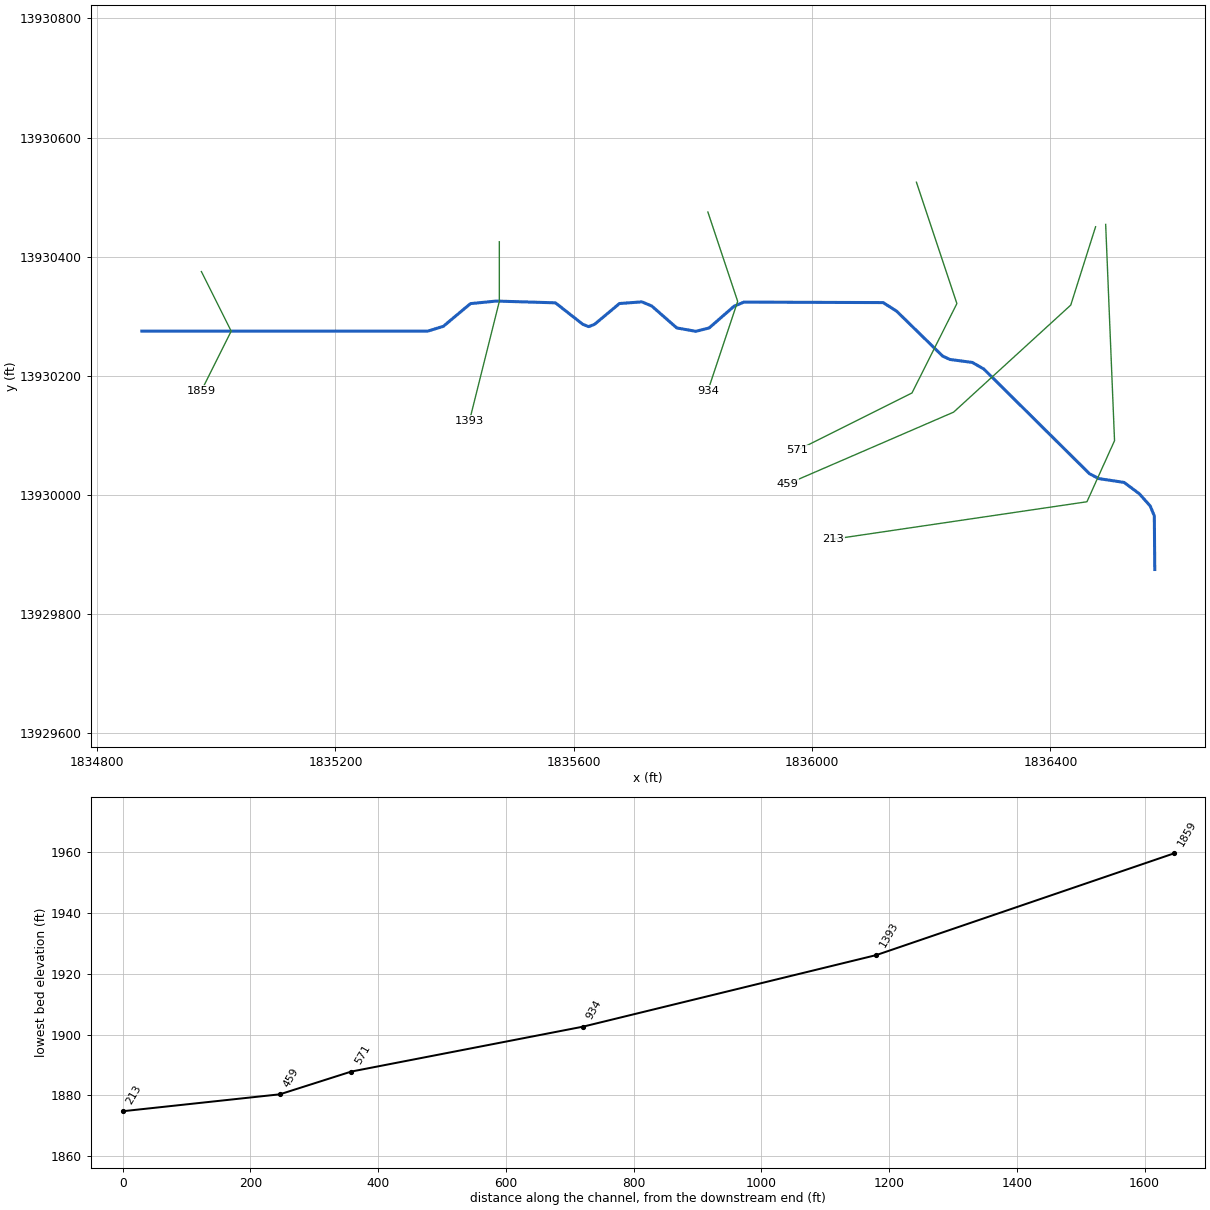
--- Stream0201.prj (project) ---

Proj Title=Stream0201 Base Level Engineering
Current Plan=p01
Default Exp/Contr=0.3,0.1
English Units
Geom File=g01
Flow File=f01
Plan File=p01
Y Axis Title=Elevation
X Axis Title(PF)=Main Channel Distance
X Axis Title(XS)=Station
BEGIN DESCRIPTION:
Stream0201
END DESCRIPTION:
DSS Export Rating Curves= 0
DSS Export Rating Curve Sorted= 0
DSS Export Volume Flow Curves= 0
DXF OffsetX= 0
DXF OffsetY= 0
DXF ScaleX= 1
DXF ScaleY= 10

--- Stream0201.p01 (plan) ---

Plan Title=Multiple Run
Short Identifier=Multiple
Geom File=g01
Flow File=f01
Subcritical Flow
K Sum by GR= 0
Std Step Tol= 0.01
Critical Tol= 0.01
Num of Std Step Trials= 20
Max Error Tol= 0.3
Flow Tol Ratio= 0.001
Split Flow NTrial= 30
Split Flow Tol= 0.02
Split Flow Ratio= 0.02
Log Output Level= 0
Friction Slope Method= 1
Unsteady Friction Slope Method= 2
Unsteady Bridges Friction Slope Method= 1
Parabolic Critical Depth
Global Vel Dist=  1 , 1 , 1
Global Log Level= 0
CheckData=True
Encroach Param= -1, 0, 0, 0
BEGIN DESCRIPTION:
Multiple Run
END DESCRIPTION:

--- Stream0201.f01 (steady flow) ---

Flow Title=Multiple
Program Version=4.10
Number of Profiles= 7
Profile Names=10-year,25-year,50-year,1pct_min,100-year,1pct_plu,500-year
River Rch & RM=Stream0201,Reach-1         ,1859
     191     291     377     239     476     950     742
Boundary for River Rch & Prof#=Stream0201,Reach-1         , 1
Up Type= 0
Dn Type= 3
Dn Slope=0.003
Boundary for River Rch & Prof#=Stream0201,Reach-1         , 2
Up Type= 0
Dn Type= 3
Dn Slope=0.003
Boundary for River Rch & Prof#=Stream0201,Reach-1         , 3
Up Type= 0
Dn Type= 3
Dn Slope=0.003
Boundary for River Rch & Prof#=Stream0201,Reach-1         , 4
Up Type= 0
Dn Type= 3
Dn Slope=0.003
Boundary for River Rch & Prof#=Stream0201,Reach-1         , 5
Up Type= 0
Dn Type= 3
Dn Slope=0.003
Boundary for River Rch & Prof#=Stream0201,Reach-1         , 6
Up Type= 0
Dn Type= 3
Dn Slope=0.003
Boundary for River Rch & Prof#=Stream0201,Reach-1         , 7
Up Type= 0
Dn Type= 3
Dn Slope=0.003
DSS Import GetInterval= 0
DSS Import GetPeak= 0
DSS Import FillOption= 0

--- Stream0201.g01 (geometry) ---

Geom Title=Existing Conditions
Program Version=4.10

River Reach=Stream0201      ,Reach-1
Reach XY= 30
        1834875.       13930275.      1835354.97     13930275.07
      1835381.06     13930283.14      1835426.57     13930321.23
      1835469.84      13930325.5      1835569.14     13930322.55
       1835615.1     13930286.49      1835625.01     13930282.59
      1835634.93     13930286.53      1835676.64     13930321.39
       1835714.3     13930324.16      1835730.93     13930317.12
       1835772.8     13930280.41      1835804.82     13930274.72
      1835827.18     13930280.38      1835868.92     13930316.81
       1835885.5     13930323.76      1836119.14     13930322.94
      1836141.75     13930308.54      1836218.96     13930233.18
      1836231.05     13930227.54      1836268.95     13930222.47
      1836288.21     13930211.37      1836465.34     13930035.78
      1836481.09     13930027.55      1836523.59     13930021.13
      1836548.96     13930002.22       1836567.4     13929981.55
      1836574.26     13929964.85        1836575.       13929875.

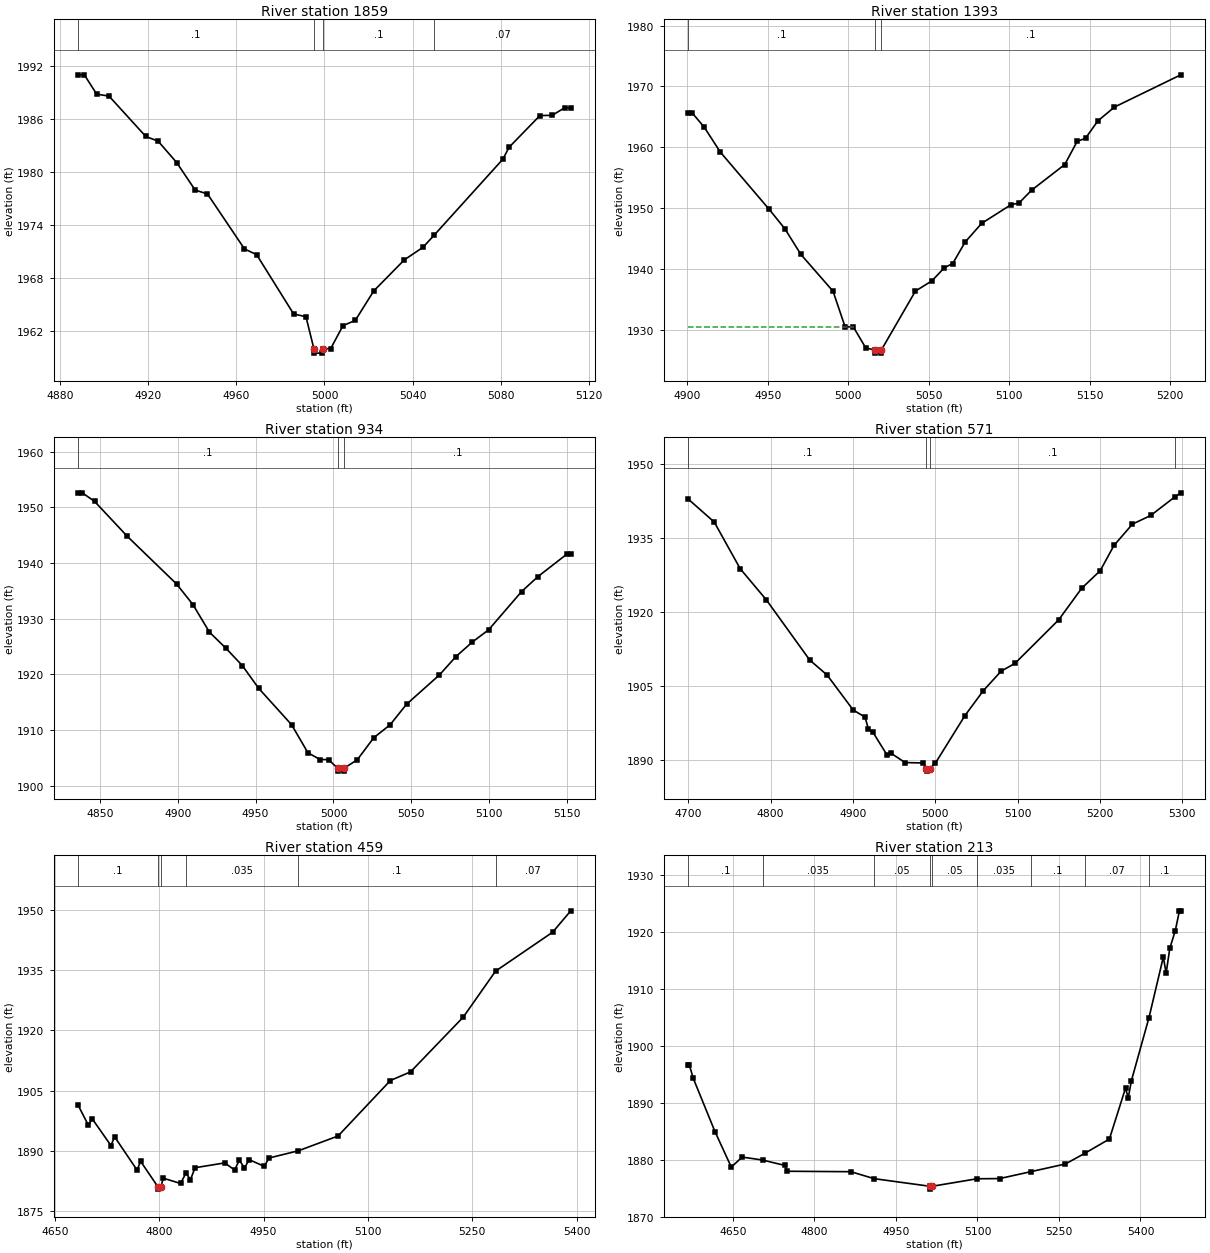
Type RM Length L Ch R = 1 ,1859    ,466,466,466
BEGIN DESCRIPTION:
Stream0201 4.0
END DESCRIPTION:
XS GIS Cut Line= 3
      1834975.01     13930374.99        1835025.       13930275.
        1834975.     13930174.99
#Sta/Elev= 30
  4888.2 1990.95    4891 1990.95  4896.6 1988.77  4902.2 1988.55  4918.9 1983.99
  4924.5 1983.46  4932.9 1981.05  4941.3 1977.94  4946.9  1977.5  4963.7 1971.29
  4969.2 1970.65    4986 1963.95  4991.6 1963.64  4995.2 1960.03  4995.4 1959.53
  4998.9 1959.53  4999.2 1960.03  5002.8 1960.03  5008.4 1962.63    5014 1963.23
  5022.4 1966.56  5036.3 1970.07  5044.7 1971.47  5049.8 1972.85    5081 1981.43
  5083.8 1982.77  5097.8 1986.35  5103.4 1986.38    5109 1987.23  5111.8 1987.23
#Mann= 4 ,-1 , 0
  4888.2      .1       0  4995.2     .05       0  4999.2      .1       0
  5049.8     .07       0
Bank Sta=4995.2,4999.2
XS Rating Curve= 0 ,0
Exp/Cntr=0.3,0.1

Type RM Length L Ch R = 1 ,1393    ,459,459,459
BEGIN DESCRIPTION:
Stream0201 3.0
END DESCRIPTION:
XS GIS Cut Line= 3
        1835475.     13930424.98        1835475.       13930325.
      1835425.01     13930125.03
#Sta/Elev= 30
  4900.5 1965.62    4903 1965.62  4910.5 1963.26  4920.5 1959.17  4950.5 1949.87
  4960.5  1946.6  4970.5 1942.36  4990.5  1936.3    4998 1930.44  5003.1 1930.44
  5010.8 1926.99  5016.5 1926.62  5016.8 1926.12  5020.3 1926.12  5020.5 1926.62
  5041.7 1936.32    5052 1938.02  5059.7 1940.17  5064.9 1940.86  5072.6 1944.39
  5082.9 1947.47    5101 1950.51  5106.1 1950.81  5113.9 1952.92  5134.5 1957.14
  5142.2 1960.94  5147.4 1961.46  5155.1 1964.32  5165.4 1966.59  5206.6 1971.89
#Mann= 3 ,-1 , 0
  4900.5      .1       0  5016.5     .05       0  5020.5      .1       0
#XS Ineff= 2 , 0
         5003.24 1930.46
Permanent Ineff=
       F       F
Bank Sta=5016.5,5020.5
XS Rating Curve= 0 ,0
Exp/Cntr=0.3,0.1

Type RM Length L Ch R = 1 ,934     ,363,363,363
BEGIN DESCRIPTION:
Stream0201 2.0
END DESCRIPTION:
XS GIS Cut Line= 3
      1835825.01     13930474.96        1835875.       13930325.
        1835825.     13930174.99
#Sta/Elev= 30
  4836.1 1952.58  4838.7 1952.58  4846.6 1951.05  4867.7 1944.75  4899.3  1936.2
  4909.8  1932.5  4920.4 1927.55  4930.9 1924.69  4941.5 1921.55    4952 1917.47
  4973.1 1910.94  4983.6  1905.9  4991.5 1904.68  4996.8 1904.68  5002.7 1903.11
    5003 1902.61  5006.5 1902.61  5006.7 1903.11  5015.3 1904.66  5025.8 1908.59
  5036.3 1910.92  5046.9 1914.62    5068 1919.88  5078.5 1923.15    5089 1925.76
  5099.6 1927.99  5120.7 1934.84  5131.2 1937.53  5149.7 1941.55  5152.3 1941.55
#Mann= 3 ,-1 , 0
  4836.1      .1       0  5002.7     .05       0  5006.7      .1       0
Bank Sta=5002.7,5006.7
XS Rating Curve= 0 ,0
Exp/Cntr=0.3,0.1

Type RM Length L Ch R = 1 ,571     ,112,112,112
BEGIN DESCRIPTION:
Stream0201 1.0
END DESCRIPTION:
XS GIS Cut Line= 4
      1836175.01     13930524.97       1836242.9     13930321.29
      1836167.55     13930171.27      1835974.96     13930074.98
#Sta/Elev= 30
  4700.1 1942.86  4731.7 1938.21  4763.3 1928.76  4794.9 1922.49  4847.6 1910.31
  4868.7 1907.28  4900.3 1900.22  4914.8 1898.76  4918.8 1896.35  4924.3 1895.72
  4941.1  1891.2  4946.7 1891.42  4963.4 1889.58  4985.7  1889.5  4989.3 1888.35
  4989.6 1887.85  4993.3 1888.35  5000.2 1889.48    5036 1899.08  5058.3 1904.11
  5079.9 1908.06  5096.7 1909.63  5149.8 1918.44  5177.8 1924.84  5200.1 1928.35
  5216.9 1933.48  5239.3 1937.79  5261.6 1939.55  5290.7 1943.29    5298 1944.12
#Mann= 4 ,-1 , 0
  4700.1      .1       0  4989.3     .05       0  4993.3      .1       0
  5290.7     .07       0
Bank Sta=4989.3,4993.3
XS Rating Curve= 0 ,0
Exp/Cntr=0.3,0.1

Type RM Length L Ch R = 1 ,459     ,246,246,246
BEGIN DESCRIPTION:
Stream0201 0.3
END DESCRIPTION:
XS GIS Cut Line= 4
      1836475.68     13930450.25      1836434.01     13930318.75
       1836237.4     13930139.07      1835958.75     13930018.53
#Sta/Elev= 30
  4683.5 1901.31  4698.3 1896.28  4703.5 1897.99  4730.6 1891.25  4735.8 1893.45
  4768.1 1885.14  4773.3  1887.3  4798.4 1880.87  4798.6 1880.37  4802.4 1880.87
  4805.6 1883.11  4830.6 1881.79  4838.5  1884.4  4844.8 1882.72  4851.6 1885.72
  4894.2 1886.92  4908.3 1885.15  4915.1  1887.6  4922.5 1885.68  4929.3 1887.73
  4950.9 1886.06  4957.7 1888.14    5000 1889.95    5057 1893.64  5132.2  1907.5
  5161.1 1909.65    5237 1923.35  5283.3 1934.81  5365.4 1944.55  5391.4 1949.88
#Mann= 6 ,-1 , 0
  4683.5      .1       0  4798.4     .05       0  4802.4      .1       0
  4838.5    .035       0    5000      .1       0  5283.3     .07       0
Bank Sta=4798.4,4802.4
XS Rating Curve= 0 ,0
Exp/Cntr=0.3,0.1

Type RM Length L Ch R = 1 ,213     ,0,0,0
BEGIN DESCRIPTION:
Stream0201 0.0
END DESCRIPTION:
XS GIS Cut Line= 4
       1836492.6     13930454.19      1836507.48     13930091.23
       1836461.2     13929988.69      1836034.98      13929925.8
#Sta/Elev= 30
  4567.6 1896.63  4569.7 1896.63  4576.8  1894.3  4616.8 1884.93  4646.9 1878.68
  4666.9 1880.44  4704.6 1879.92  4745.1 1878.98  4750.1 1877.95    4867 1877.87
  4909.8 1876.65  5012.5 1875.31  5012.7 1874.81  5016.5 1875.31  5099.2 1876.63
  5140.6 1876.66  5198.4 1877.88  5261.9 1879.23  5297.5  1881.1  5342.8 1883.61
  5372.5 1892.56  5377.5 1890.83  5383.2 1893.82  5415.7 1904.95  5442.1  1915.6
  5447.2 1912.73    5454 1917.13  5464.1 1920.22  5471.7  1923.7  5474.2  1923.7
#Mann= 9 ,-1 , 0
  4567.6      .1       0  4704.6    .035       0  4909.8     .05       0
  5012.5     .05       0  5016.5     .05       0  5099.2    .035       0
  5198.4      .1       0  5297.5     .07       0  5415.7      .1       0
Bank Sta=5012.5,5016.5
XS Rating Curve= 0 ,0
Exp/Cntr=0.3,0.1

Chan Stop Cuts=-1
Use User Specified Reach Order=0
Composite Channel Slope=5