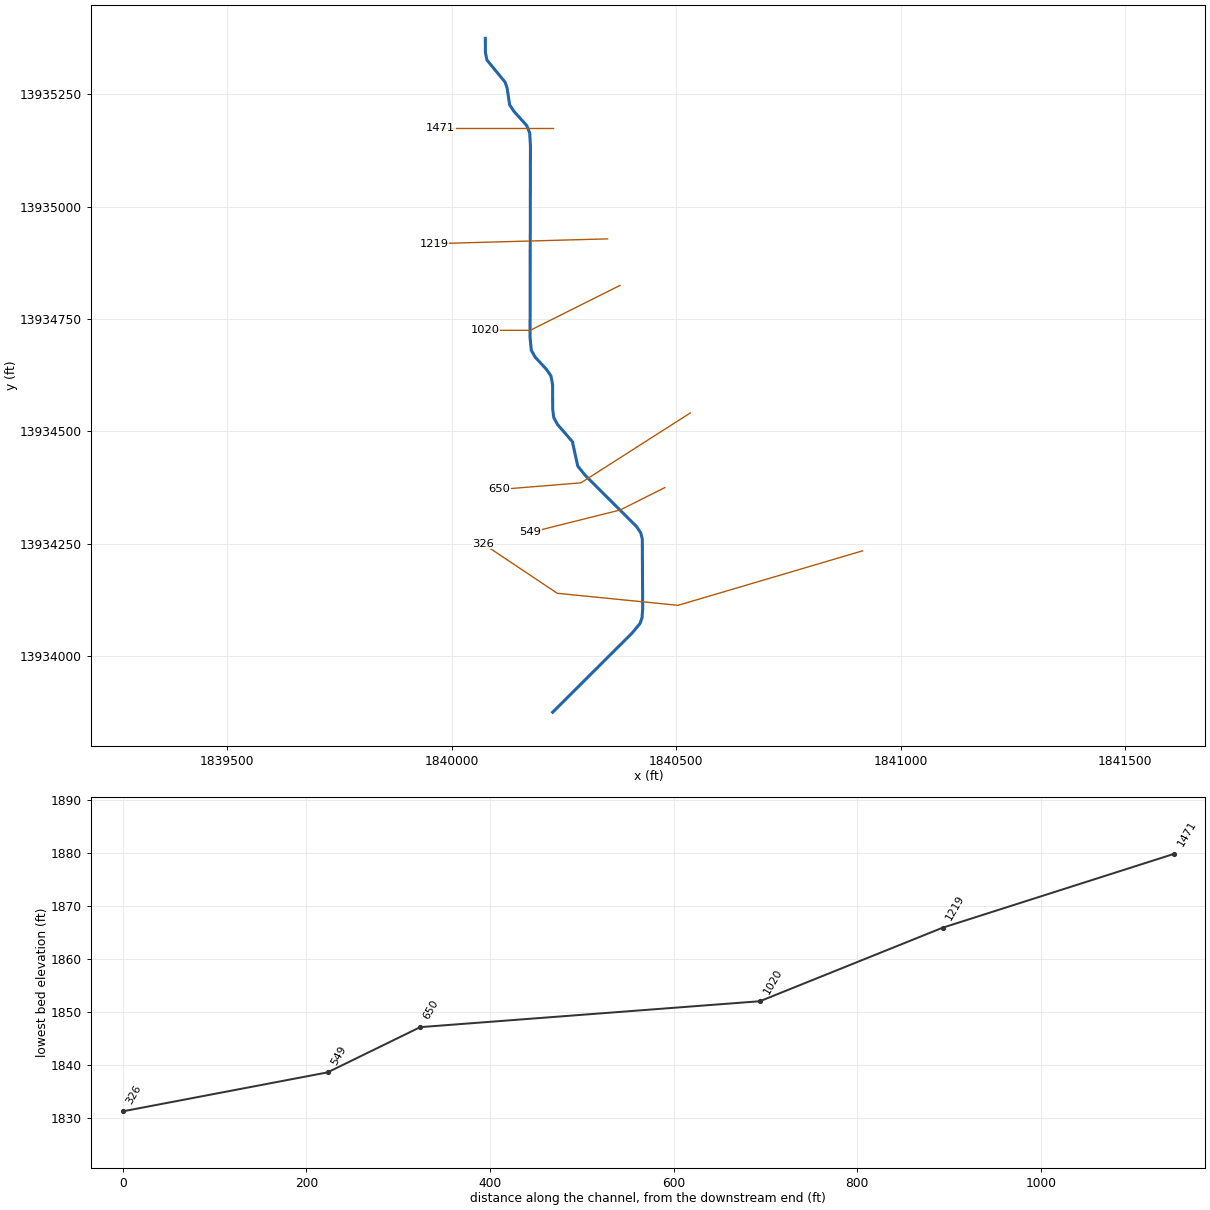
--- Stream0202.prj (project) ---

Proj Title=Stream0202 Base Level Engineering
Current Plan=p01
Default Exp/Contr=0.3,0.1
English Units
Geom File=g01
Flow File=f01
Plan File=p01
BEGIN DESCRIPTION:
Stream0202
END DESCRIPTION:

--- Stream0202.p01 (plan) ---

Plan Title=Multiple Run
Short Identifier=Multiple
Geom File=g01
Flow File=f01
Subcritical Flow
K Sum by GR= 0
Std Step Tol= 0.01
Critical Tol= 0.01
Num of Std Step Trials= 20
Max Error Tol= 0.3
Flow Tol Ratio= 0.001
Split Flow NTrial= 30
Split Flow Tol= 0.02
Split Flow Ratio= 0.02
Log Output Level= 0
Friction Slope Method= 1
Unsteady Friction Slope Method= 2
Unsteady Bridges Friction Slope Method= 1
Parabolic Critical Depth
Global Vel Dist=  1 , 1 , 1
Global Log Level= 0
CheckData=True
Encroach Param= -1, 0, 0, 0
BEGIN DESCRIPTION:
Multiple Run
END DESCRIPTION:

--- Stream0202.f01 (steady flow) ---

Flow Title=Multiple
Number of Profiles=7
Profile Names=10-year,25-year,50-year,1pct_min,100-year,1pct_plu,500-year
River Rch & RM= Stream0202,Reach-1,1471
     347     556     746     487     972    1939    1621
Boundary for River Rch & Prof#=Stream0202,Reach-1,1
Up Type=0
Dn Type=3
Dn Slope=0.005
Boundary for River Rch & Prof#=Stream0202,Reach-1,2
Up Type=0
Dn Type=3
Dn Slope=0.005
Boundary for River Rch & Prof#=Stream0202,Reach-1,3
Up Type=0
Dn Type=3
Dn Slope=0.005
Boundary for River Rch & Prof#=Stream0202,Reach-1,4
Up Type=0
Dn Type=3
Dn Slope=0.005
Boundary for River Rch & Prof#=Stream0202,Reach-1,5
Up Type=0
Dn Type=3
Dn Slope=0.005
Boundary for River Rch & Prof#=Stream0202,Reach-1,6
Up Type=0
Dn Type=3
Dn Slope=0.005
Boundary for River Rch & Prof#=Stream0202,Reach-1,7
Up Type=0
Dn Type=3
Dn Slope=0.005

--- Stream0202.g01 (geometry) ---

Geom Title=Existing Conditions

River Reach=Stream0202,Reach-1
Reach XY= 30
      1840075.00     13935375.00      1840075.10     13935343.19
      1840078.60     13935326.49      1840119.05     13935277.25
      1840123.39     13935264.33      1840129.17     13935226.73
      1840139.04     13935211.96      1840166.91     13935181.08
      1840173.80     13935164.50      1840175.46     13935135.19
      1840174.57     13934709.82      1840177.26     13934680.94
      1840185.85     13934665.35      1840211.17     13934638.13
      1840221.14     13934623.40      1840224.76     13934604.90
      1840224.99     13934550.00      1840227.33     13934530.97
      1840235.84     13934515.35      1840268.86     13934477.17
      1840280.83     13934422.70      1840298.01     13934401.53
      1840411.63     13934288.32      1840421.46     13934273.54
      1840424.62     13934259.84      1840425.44     13934104.82
      1840423.95     13934085.43      1840419.54     13934072.55
      1840402.14     13934051.47      1840225.00     13933875.00

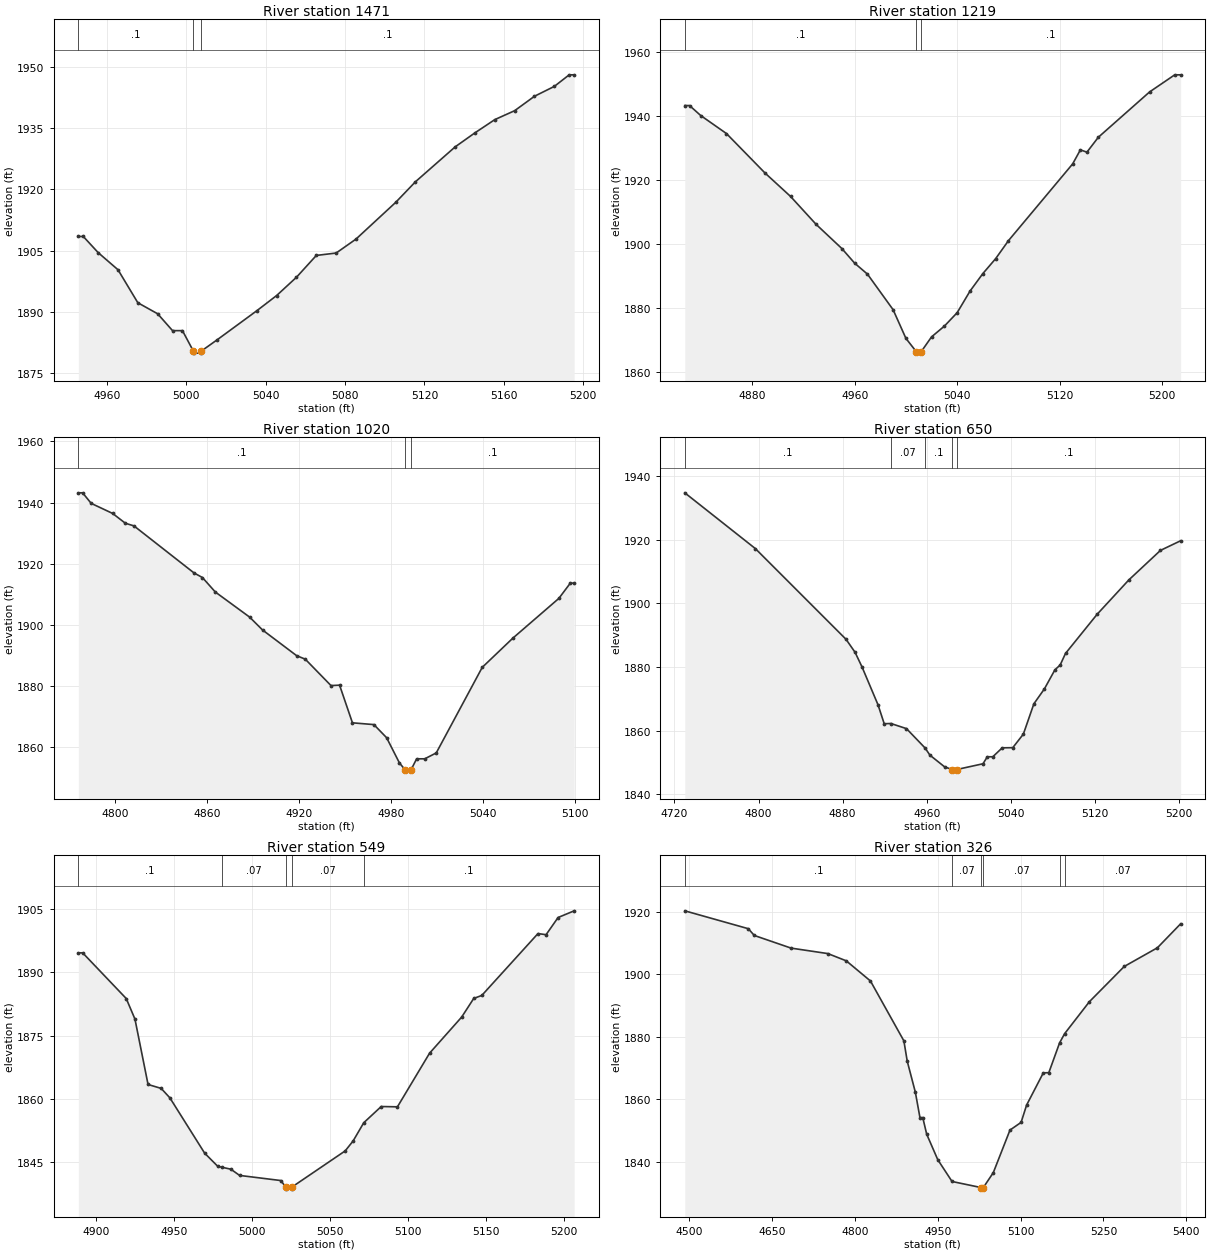
Type RM Length L Ch R = 1,1471,252,252,252
BEGIN DESCRIPTION:
Stream0202 3.0
END DESCRIPTION:
XS GIS Cut Line= 3
      1840224.97     13935175.00      1840175.00     13935175.00
      1839974.97     13935175.00
#Sta/Elev= 29
  4945.5 1908.44  4948.0 1908.44  4955.5 1904.49  4965.5 1900.30  4975.5 1892.23
  4985.5 1889.53  4993.0 1885.41  4998.0 1885.41  5003.5 1880.41  5003.7 1879.91
  5007.2 1879.91  5007.5 1880.41  5015.5 1883.17  5035.5 1890.28  5045.5 1894.00
  5055.5 1898.47  5065.5 1903.80  5075.5 1904.39  5085.5 1907.80  5105.5 1916.77
  5115.5 1921.83  5135.5 1930.35  5145.5 1933.79  5155.5 1937.02  5165.5 1939.20
  5175.5 1942.73  5185.5 1945.14  5193.0 1947.97  5195.5 1947.97
#Mann=3,-1,0
  4945.5     0.1       0  5003.5    0.05       0  5007.5     0.1       0
Bank Sta=5003.5,5007.5
Exp/Cntr=0.3,0.1

Type RM Length L Ch R = 1,1219,199,199,199
BEGIN DESCRIPTION:
Stream0202 2.1
END DESCRIPTION:
XS GIS Cut Line= 2
      1840347.44     13934928.54      1839960.79     13934917.88
#Sta/Elev= 30
  4827.5 1943.34  4831.2 1943.34  4839.9 1940.23  4860.0 1934.59  4890.0 1922.29
  4910.0 1914.94  4930.0 1906.19  4950.0 1898.67  4960.0 1894.09  4970.0 1890.66
  4990.0 1879.55  5000.0 1870.59  5008.0 1866.48  5008.3 1865.98  5011.8 1865.98
  5012.0 1866.48  5020.0 1871.06  5030.0 1874.42  5040.0 1878.63  5050.0 1885.36
  5060.0 1890.83  5070.0 1895.50  5080.0 1901.13  5130.1 1925.12  5136.1 1929.50
  5141.2 1928.77  5150.1 1933.43  5190.1 1947.60  5209.7 1952.94  5214.3 1952.94
#Mann=3,-1,0
  4827.5     0.1       0  5008.0    0.05       0  5012.0     0.1       0
Bank Sta=5008,5012
Exp/Cntr=0.3,0.1

Type RM Length L Ch R = 1,1020,370,370,370
BEGIN DESCRIPTION:
Stream0202 2.0
END DESCRIPTION:
XS GIS Cut Line= 3
      1840374.99     13934825.00      1840175.00     13934725.00
      1840075.00     13934725.00
#Sta/Elev= 30
  4776.0 1943.20  4778.8 1943.20  4784.4 1939.75  4798.4 1936.45  4806.7 1933.24
  4812.3 1932.38  4851.5 1916.98  4857.0 1915.47  4865.4 1910.74  4887.8 1902.52
  4896.2 1898.32  4918.5 1889.89  4924.1 1888.76  4940.9 1880.11  4946.5 1880.25
  4954.9 1867.92  4968.9 1867.34  4977.2 1863.05  4985.6 1854.76  4989.2 1852.61
  4989.5 1852.11  4993.2 1852.61  4996.8 1856.14  5002.1 1856.14  5009.6 1858.07
  5039.6 1886.07  5059.6 1895.64  5089.6 1908.64  5097.1 1913.64  5099.6 1913.64
#Mann=3,-1,0
  4776.0     0.1       0  4989.2    0.05       0  4993.2     0.1       0
Bank Sta=4989.2,4993.2
Exp/Cntr=0.3,0.1

Type RM Length L Ch R = 1,650,101,101,101
BEGIN DESCRIPTION:
Stream0202 1.1
END DESCRIPTION:
XS GIS Cut Line= 3
      1840531.52     13934541.09      1840287.83     13934385.51
      1840105.85     13934370.70
#Sta/Elev= 30
  4729.8 1934.84  4796.9 1917.29  4883.2 1888.72  4891.8 1884.62  4898.4 1880.02
  4913.6 1868.12  4919.5 1862.15  4925.9 1862.21  4940.7 1860.60  4958.4 1854.50
  4963.0 1852.25  4977.1 1848.53  4984.4 1847.72  4984.6 1847.22  4988.4 1847.72
  5013.5 1849.54  5017.6 1851.74  5022.8 1851.74  5031.8 1854.56  5041.8 1854.60
  5051.9 1858.88  5061.9 1868.42  5071.9 1873.11  5081.9 1879.11  5086.9 1880.63
  5092.0 1884.28  5122.1 1896.61  5152.2 1907.41  5182.3 1916.71  5201.5 1919.75
#Mann=5,-1,0
  4729.8     0.1       0  4925.9    0.07       0  4958.4     0.1       0
  4984.4    0.05       0  4988.4     0.1       0
Bank Sta=4984.4,4988.4
Exp/Cntr=0.3,0.1

Type RM Length L Ch R = 1,549,223,223,223
BEGIN DESCRIPTION:
Stream0202 1.0
END DESCRIPTION:
XS GIS Cut Line= 3
      1840474.98     13934374.99      1840375.00     13934325.00
      1840175.04     13934275.01
#Sta/Elev= 30
  4888.5 1894.54  4891.3 1894.54  4919.2 1883.75  4924.8 1878.89  4933.2 1863.42
  4941.6 1862.50  4947.2 1860.26  4969.5 1847.18  4977.9 1844.07  4980.6 1843.85
  4986.3 1843.39  4991.9 1841.92  5018.3 1840.71  5021.5 1839.18  5021.7 1838.68
  5025.2 1838.68  5025.5 1839.18  5059.6 1847.72  5064.7 1850.08  5071.5 1854.38
  5082.7 1858.21  5093.1 1858.14  5113.7 1870.82  5134.3 1879.37  5142.0 1883.76
  5147.2 1884.48  5183.2 1899.10  5188.4 1898.84  5196.1 1902.90  5206.4 1904.48
#Mann=5,-1,0
  4888.5     0.1       0  4980.6    0.07       0  5021.5    0.05       0
  5025.5    0.07       0  5071.5     0.1       0
Bank Sta=5021.5,5025.5
Exp/Cntr=0.3,0.1

Type RM Length L Ch R = 1,326,0,0,0
BEGIN DESCRIPTION:
Stream0202 0.0
END DESCRIPTION:
XS GIS Cut Line= 4
      1840915.34     13934234.22      1840504.14     13934112.88
      1840235.24     13934139.68      1840070.05     13934250.00
#Sta/Elev= 30
  4492.2 1920.23  4607.2 1914.52  4618.0 1912.36  4684.6 1908.32  4751.2 1906.57
  4784.5 1904.26  4828.3 1897.82  4888.8 1878.69  4894.9 1872.19  4909.6 1862.27
  4917.9 1854.18  4923.0 1854.18  4930.1 1848.88  4950.2 1840.72  4976.0 1833.77
  5028.6 1831.83  5028.9 1831.33  5032.6 1831.83  5050.7 1836.60  5080.9 1850.20
  5101.0 1852.65  5111.0 1858.19  5141.2 1868.47  5151.2 1868.53  5170.7 1878.05
  5179.8 1880.99  5224.6 1891.19  5287.7 1902.45  5347.8 1908.43  5389.8 1916.08
#Mann=6,-1,0
  4492.2     0.1       0  4976.0    0.07       0  5028.6    0.05       0
  5032.6    0.07       0  5170.7     0.1       0  5179.8    0.07       0
Bank Sta=5028.6,5032.6
Exp/Cntr=0.3,0.1

Chan Stop Cuts=-1