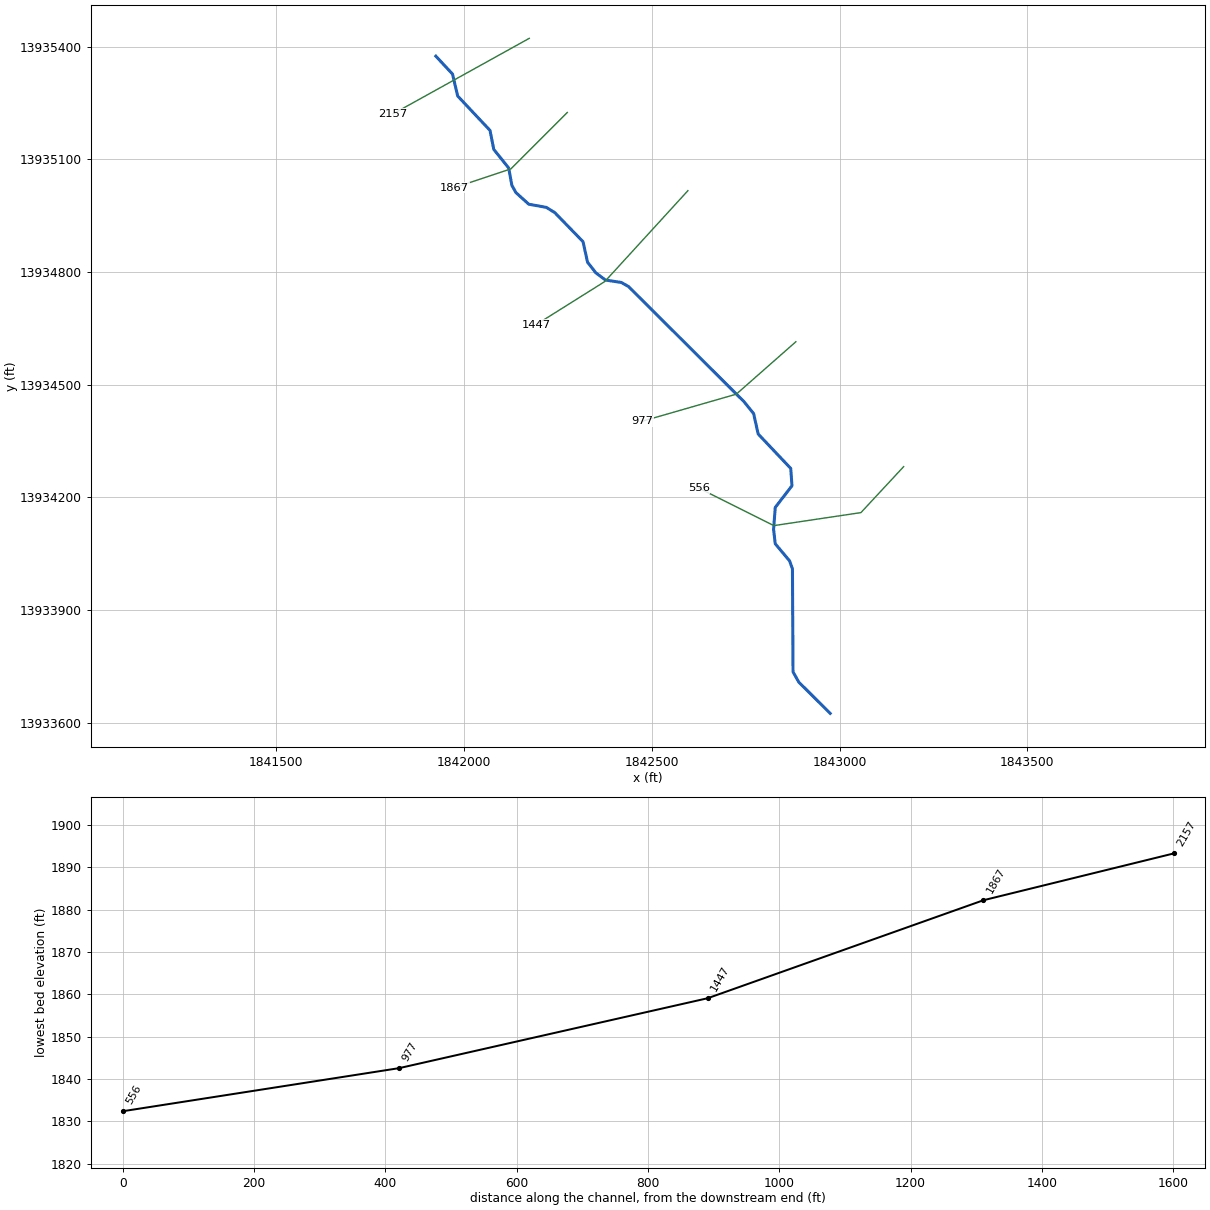
--- Stream0203.prj (project) ---

Proj Title=Stream0203 Base Level Engineering
Current Plan=p01
Default Exp/Contr=0.3,0.1
English Units
Geom File=g01
Flow File=f01
Plan File=p01
BEGIN DESCRIPTION:
Stream0203
END DESCRIPTION:

--- Stream0203.p01 (plan) ---

Plan Title=Multiple Run
Short Identifier=Multiple
Geom File=g01
Flow File=f01
Subcritical Flow
K Sum by GR= 0
Std Step Tol= 0.01
Critical Tol= 0.01
Num of Std Step Trials= 20
Max Error Tol= 0.3
Flow Tol Ratio= 0.001
Split Flow NTrial= 30
Split Flow Tol= 0.02
Split Flow Ratio= 0.02
Log Output Level= 0
Friction Slope Method= 1
Unsteady Friction Slope Method= 2
Unsteady Bridges Friction Slope Method= 1
Parabolic Critical Depth
Global Vel Dist=  1 , 1 , 1
Global Log Level= 0
CheckData=True
Encroach Param= -1, 0, 0, 0
BEGIN DESCRIPTION:
Multiple Run
END DESCRIPTION:

--- Stream0203.f01 (steady flow) ---

Flow Title=Multiple
Number of Profiles=7
Profile Names=10-year,25-year,50-year,1pct_min,100-year,1pct_plu,500-year
River Rch & RM= Stream0203,Reach-1,2157
     365     585     783     510    1018    2031    1692
Boundary for River Rch & Prof#=Stream0203,Reach-1,1
Up Type=0
Dn Type=3
Dn Slope=0.005
Boundary for River Rch & Prof#=Stream0203,Reach-1,2
Up Type=0
Dn Type=3
Dn Slope=0.005
Boundary for River Rch & Prof#=Stream0203,Reach-1,3
Up Type=0
Dn Type=3
Dn Slope=0.005
Boundary for River Rch & Prof#=Stream0203,Reach-1,4
Up Type=0
Dn Type=3
Dn Slope=0.005
Boundary for River Rch & Prof#=Stream0203,Reach-1,5
Up Type=0
Dn Type=3
Dn Slope=0.005
Boundary for River Rch & Prof#=Stream0203,Reach-1,6
Up Type=0
Dn Type=3
Dn Slope=0.005
Boundary for River Rch & Prof#=Stream0203,Reach-1,7
Up Type=0
Dn Type=3
Dn Slope=0.005

--- Stream0203.g01 (geometry) ---

Geom Title=Existing Conditions

River Reach=Stream0203,Reach-1
Reach XY= 30
      1841925.00     13935375.00      1841969.30     13935327.35
      1841983.07     13935268.92      1842069.15     13935177.29
      1842079.19     13935126.73      1842118.89     13935077.16
      1842127.42     13935030.85      1842138.47     13935011.43
      1842172.46     13934980.75      1842218.92     13934972.45
      1842241.70     13934958.36      1842316.84     13934881.05
      1842328.89     13934826.43      1842351.16     13934797.86
      1842376.43     13934778.89      1842418.91     13934772.45
      1842438.20     13934761.36      1842745.38     13934455.16
      1842771.03     13934423.35      1842783.18     13934368.96
      1842869.90     13934277.29      1842873.21     13934231.13
      1842828.74     13934173.42      1842824.23     13934114.95
      1842828.71     13934076.60      1842866.85     13934031.06
      1842874.48     13934009.78      1842876.02     13933735.42
      1842891.33     13933708.19      1842975.00     13933625.00

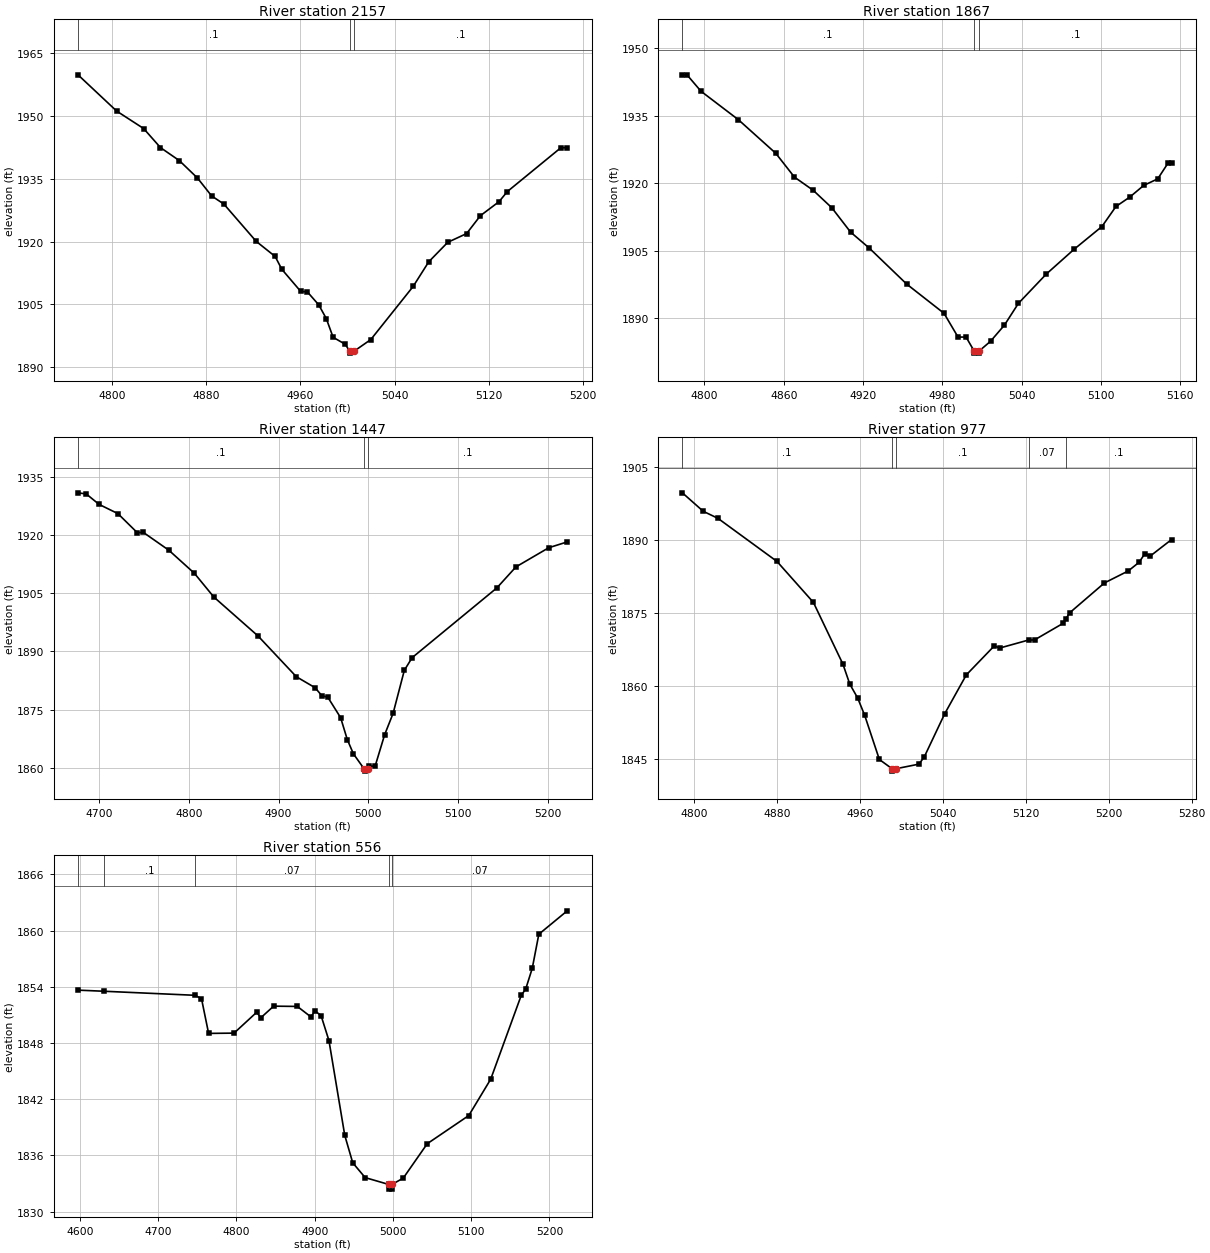
Type RM Length L Ch R = 1,2157,290,290,290
BEGIN DESCRIPTION:
Stream0203 5.0
END DESCRIPTION:
XS GIS Cut Line= 2
      1842173.72     13935422.51      1841810.58     13935221.21
#Sta/Elev= 30
  4771.3 1959.88  4804.1 1951.21  4827.0 1947.03  4841.3 1942.47  4857.3 1939.36
  4872.7 1935.19  4884.7 1930.91  4895.1 1928.96  4922.5 1920.05  4938.6 1916.43
  4944.3 1913.35  4960.3 1908.07  4966.0 1907.94  4975.6 1904.85  4982.0 1901.58
  4987.8 1897.09  4998.1 1895.42  5001.8 1893.80  5002.0 1893.30  5005.8 1893.80
  5019.8 1896.55  5055.7 1909.24  5069.0 1915.16  5085.1 1919.81  5101.1 1921.90
  5112.8 1926.18  5128.6 1929.53  5135.7 1931.96  5181.1 1942.44  5186.5 1942.44
#Mann=3,-1,0
  4771.3     0.1       0  5001.8    0.05       0  5005.8     0.1       0
Bank Sta=5001.8,5005.8
Exp/Cntr=0.3,0.1

Type RM Length L Ch R = 1,1867,420,420,420
BEGIN DESCRIPTION:
Stream0203 4.0
END DESCRIPTION:
XS GIS Cut Line= 3
      1842274.99     13935224.99      1842125.00     13935075.00
      1841975.02     13935025.01
#Sta/Elev= 30
  4783.3 1944.11  4786.8 1944.11  4797.4 1940.46  4825.7 1934.13  4854.0 1926.66
  4868.1 1921.37  4882.3 1918.44  4896.4 1914.55  4910.6 1909.14  4924.7 1905.60
  4953.0 1897.60  4981.3 1891.09  4991.9 1885.81  4998.0 1885.81  5004.0 1882.74
  5004.2 1882.24  5007.7 1882.24  5008.0 1882.74  5016.5 1884.88  5027.0 1888.46
  5037.6 1893.31  5058.7 1899.82  5079.7 1905.32  5100.8 1910.39  5111.4 1914.84
  5121.9 1916.94  5132.4 1919.52  5143.0 1920.98  5150.9 1924.53  5153.5 1924.53
#Mann=3,-1,0
  4783.3     0.1       0  5004.0    0.05       0  5008.0     0.1       0
Bank Sta=5004,5008
Exp/Cntr=0.3,0.1

Type RM Length L Ch R = 1,1447,470,470,470
BEGIN DESCRIPTION:
Stream0203 3.0
END DESCRIPTION:
XS GIS Cut Line= 3
      1842596.13     13935016.91      1842375.00     13934775.00
      1842191.42     13934659.77
#Sta/Elev= 30
  4676.8 1930.99  4686.0 1930.70  4700.2 1928.01  4721.2 1925.62  4742.8 1920.69
  4749.5 1920.77  4777.9 1916.16  4806.3 1910.21  4827.9 1904.09  4877.2 1894.00
  4919.8 1883.48  4940.7 1880.64  4948.1 1878.60  4954.9 1878.16  4969.1 1872.90
  4976.5 1867.25  4983.3 1863.57  4995.5 1859.59  4995.7 1859.09  4999.5 1859.59
  5001.2 1860.38  5007.5 1860.38  5018.1 1868.51  5027.5 1874.02  5040.0 1885.14
  5048.7 1888.41  5143.0 1906.43  5164.2 1911.85  5200.7 1916.80  5221.3 1918.31
#Mann=3,-1,0
  4676.8     0.1       0  4995.5    0.05       0  4999.5     0.1       0
Bank Sta=4995.5,4999.5
Exp/Cntr=0.3,0.1

Type RM Length L Ch R = 1,977,421,421,421
BEGIN DESCRIPTION:
Stream0203 2.0
END DESCRIPTION:
XS GIS Cut Line= 3
      1842883.57     13934614.56      1842725.00     13934475.00
      1842474.80     13934402.98
#Sta/Elev= 30
  4789.0 1899.73  4809.1 1895.94  4823.3 1894.49  4880.2 1885.64  4915.3 1877.23
  4943.8 1864.53  4950.4 1860.44  4958.0 1857.58  4964.7 1854.06  4978.9 1844.96
  4991.1 1843.07  4991.4 1842.57  4995.1 1843.07  5017.1 1844.01  5022.3 1845.54
  5041.9 1854.36  5062.7 1862.33  5089.7 1868.30  5094.9 1867.85  5122.8 1869.50
  5128.5 1869.52  5156.3 1872.96  5158.6 1873.78  5162.2 1875.06  5195.9 1881.23
  5218.8 1883.68  5229.2 1885.45  5234.8 1887.22  5240.0 1886.74  5260.6 1890.14
#Mann=5,-1,0
  4789.0     0.1       0  4991.1    0.05       0  4995.1     0.1       0
  5122.8    0.07       0  5158.6     0.1       0
Bank Sta=4991.1,4995.1
Exp/Cntr=0.3,0.1

Type RM Length L Ch R = 1,556,0,0,0
BEGIN DESCRIPTION:
Stream0203 1.0
END DESCRIPTION:
XS GIS Cut Line= 4
      1843170.67     13934282.07      1843056.87     13934159.62
      1842825.00     13934125.00      1842625.02     13934224.99
#Sta/Elev= 30
  4597.5 1853.64  4631.2 1853.52  4746.7 1853.09  4755.3 1852.74  4764.4 1849.02
  4796.9 1849.05  4826.0 1851.29  4831.0 1850.68  4847.5 1851.93  4877.8 1851.90
  4895.2 1850.78  4900.3 1851.42  4908.1 1850.93  4918.2 1848.25  4938.4 1838.13
  4948.6 1835.20  4964.5 1833.62  4994.6 1832.89  4994.8 1832.39  4998.3 1832.39
  4998.6 1832.89  5013.1 1833.56  5043.8 1837.24  5096.9 1840.25  5124.9 1844.13
  5164.0 1853.10  5169.6 1853.75  5178.0 1855.97  5186.4 1859.61  5222.7 1862.11
#Mann=5,-1,0
  4597.5   0.035       0  4631.2     0.1       0  4746.7    0.07       0
  4994.6    0.05       0  4998.6    0.07       0
Bank Sta=4994.6,4998.6
Exp/Cntr=0.3,0.1

Chan Stop Cuts=-1