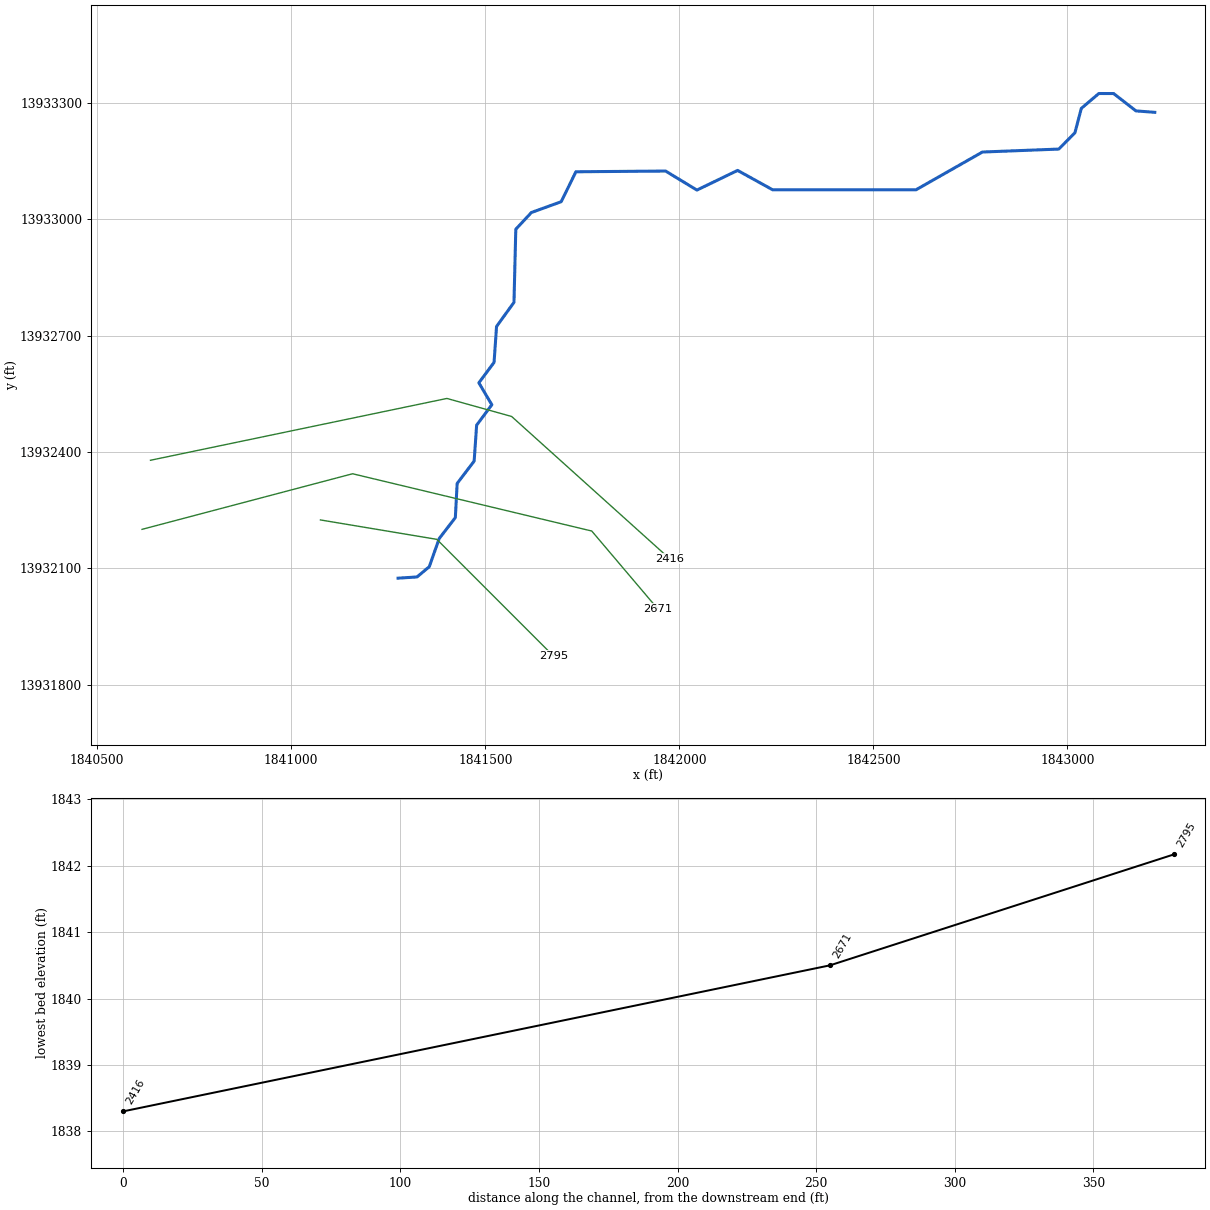
--- Stream0204.prj (project) ---

Proj Title=Stream0204 Base Level Engineering
Current Plan=p01
Default Exp/Contr=0.3,0.1
English Units
Geom File=g01
Flow File=f01
Plan File=p01
BEGIN DESCRIPTION:
Stream0204
END DESCRIPTION:

--- Stream0204.p01 (plan) ---

Plan Title=Multiple Run
Short Identifier=Multiple
Geom File=g01
Flow File=f01
Subcritical Flow
K Sum by GR= 0
Std Step Tol= 0.01
Critical Tol= 0.01
Num of Std Step Trials= 20
Max Error Tol= 0.3
Flow Tol Ratio= 0.001
Split Flow NTrial= 30
Split Flow Tol= 0.02
Split Flow Ratio= 0.02
Log Output Level= 0
Friction Slope Method= 1
Unsteady Friction Slope Method= 2
Unsteady Bridges Friction Slope Method= 1
Parabolic Critical Depth
Global Vel Dist=  1 , 1 , 1
Global Log Level= 0
CheckData=True
Encroach Param= -1, 0, 0, 0
BEGIN DESCRIPTION:
Multiple Run
END DESCRIPTION:

--- Stream0204.f01 (steady flow) ---

Flow Title=Multiple
Number of Profiles=7
Profile Names=10-year,25-year,50-year,1pct_min,100-year,1pct_plu,500-year
River Rch & RM= Stream0204,Reach-1,2795
    1573    2773    3952    2721    5429   10831   10128
Boundary for River Rch & Prof#=Stream0204,Reach-1,1
Up Type=0
Dn Type=3
Dn Slope=0.005
Boundary for River Rch & Prof#=Stream0204,Reach-1,2
Up Type=0
Dn Type=3
Dn Slope=0.005
Boundary for River Rch & Prof#=Stream0204,Reach-1,3
Up Type=0
Dn Type=3
Dn Slope=0.005
Boundary for River Rch & Prof#=Stream0204,Reach-1,4
Up Type=0
Dn Type=3
Dn Slope=0.005
Boundary for River Rch & Prof#=Stream0204,Reach-1,5
Up Type=0
Dn Type=3
Dn Slope=0.005
Boundary for River Rch & Prof#=Stream0204,Reach-1,6
Up Type=0
Dn Type=3
Dn Slope=0.005
Boundary for River Rch & Prof#=Stream0204,Reach-1,7
Up Type=0
Dn Type=3
Dn Slope=0.005

--- Stream0204.g01 (geometry) ---

Geom Title=Existing Conditions

River Reach=Stream0204,Reach-1
Reach XY= 30
      1841275.00     13932075.00      1841323.97     13932078.14
      1841355.50     13932104.53      1841381.13     13932177.16
      1841422.67     13932230.96      1841427.35     13932319.03
      1841471.15     13932376.60      1841477.54     13932469.11
      1841516.72     13932521.78      1841483.28     13932578.22
      1841522.46     13932630.89      1841528.85     13932723.40
      1841573.78     13932785.50      1841578.45     13932973.75
      1841618.64     13933016.97      1841695.42     13933044.74
      1841733.31     13933121.91      1841964.50     13933123.76
      1842045.18     13933074.72      1842150.00     13933125.39
      1842240.21     13933075.54      1842609.79     13933075.51
      1842780.93     13933172.76      1842977.70     13933180.36
      1843019.25     13933222.45      1843035.65     13933285.10
      1843080.84     13933323.49      1843118.86     13933323.42
      1843176.49     13933278.69      1843225.00     13933275.00

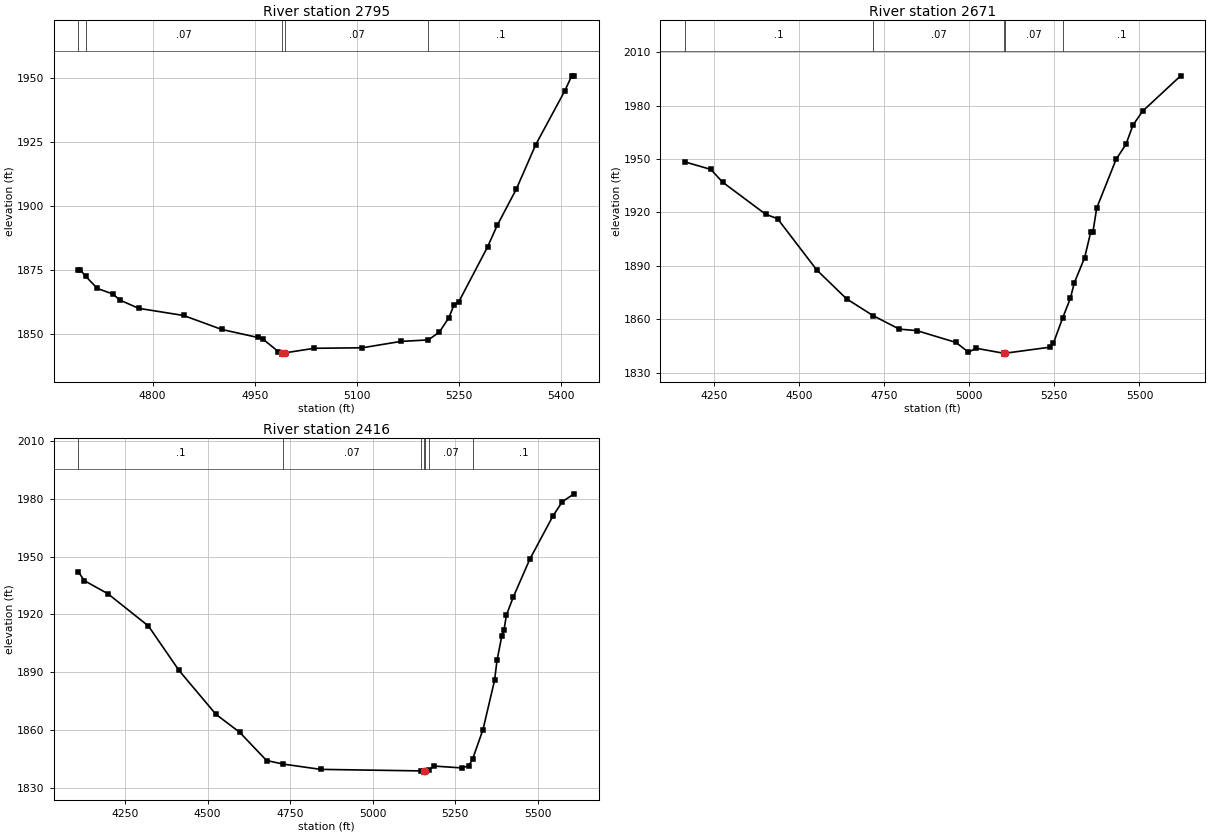
Type RM Length L Ch R = 1,2795,124,124,124
BEGIN DESCRIPTION:
Stream0204 3.0
END DESCRIPTION:
XS GIS Cut Line= 3
      1841075.01     13932225.00      1841375.00     13932175.00
      1841675.00     13931875.00
#Sta/Elev= 30
  4690.8 1875.15  4693.3 1875.15  4701.8 1872.53  4718.7 1867.83  4741.5 1865.66
  4751.6 1863.32  4779.5 1860.06  4845.4 1857.27  4901.2 1851.83  4954.4 1848.68
  4962.0 1848.04  4984.8 1843.11  4990.4 1842.67  4990.6 1842.17  4994.4 1842.67
  5037.4 1844.45  5108.1 1844.65  5164.6 1847.14  5204.9 1847.72  5221.2 1850.79
  5235.3 1856.48  5242.4 1861.22  5249.5 1862.50  5291.9 1884.01  5306.1 1892.44
  5334.3 1906.68  5362.6 1923.93  5405.1 1944.86  5415.7 1950.90  5419.2 1950.90
#Mann=5,-1,0
  4690.8     0.1       0  4701.8    0.07       0  4990.4    0.05       0
  4994.4    0.07       0  5204.9     0.1       0
Bank Sta=4990.4,4994.4
Exp/Cntr=0.3,0.1

Type RM Length L Ch R = 1,2671,255,255,255
BEGIN DESCRIPTION:
Stream0204 1.0
END DESCRIPTION:
XS GIS Cut Line= 4
      1840615.39     13932200.77      1841157.90     13932343.99
      1841774.22     13932196.42      1841943.50     13931996.77
#Sta/Elev= 30
  4164.3 1948.39  4240.6 1944.18  4275.7 1936.96  4401.8 1919.00  4436.7 1916.51
  4552.4 1887.63  4639.7 1871.51  4717.3 1862.12  4794.4 1854.53  4845.8 1853.70
  4960.7 1847.07  4997.6 1841.63  5020.6 1843.77  5100.9 1841.00  5101.1 1840.50
  5104.9 1841.00  5236.6 1844.38  5246.8 1846.48  5274.8 1861.01  5297.0 1871.82
  5308.5 1880.47  5339.0 1894.70  5357.0 1909.16  5363.4 1909.16  5374.4 1922.52
  5431.5 1949.88  5460.1 1958.16  5480.9 1969.03  5509.5 1976.90  5620.9 1996.69
#Mann=5,-1,0
  4164.3     0.1       0  4717.3    0.07       0  5100.9    0.05       0
  5104.9    0.07       0  5274.8     0.1       0
Bank Sta=5100.9,5104.9
Exp/Cntr=0.3,0.1

Type RM Length L Ch R = 1,2416,0,0,0
BEGIN DESCRIPTION:
Stream0204 2.0
END DESCRIPTION:
XS GIS Cut Line= 4
      1840637.07     13932378.72      1841400.96     13932537.98
      1841567.75     13932491.53      1841975.03     13932124.97
#Sta/Elev= 30
  4108.7 1942.09  4127.0 1937.51  4198.5 1930.69  4321.1 1913.98  4413.6 1890.98
  4525.4 1868.24  4596.9 1859.00  4678.6 1844.32  4729.1 1842.47  4842.1 1839.73
  5146.4 1838.93  5154.7 1838.80  5155.0 1838.30  5158.7 1838.80  5169.1 1839.32
  5185.1 1841.45  5270.4 1840.47  5291.3 1841.64  5302.9 1845.22  5333.9 1860.27
  5369.0 1885.81  5376.5 1896.16  5390.7 1908.60  5397.4 1911.69  5404.9 1919.64
  5425.8 1929.02  5475.5 1948.51  5546.2 1971.12  5574.6 1978.48  5610.1 1982.50
#Mann=7,-1,0
  4108.7     0.1       0  4729.1    0.07       0  5146.4     0.1       0
  5154.7    0.05       0  5158.7     0.1       0  5169.1    0.07       0
  5302.9     0.1       0
Bank Sta=5154.7,5158.7
Exp/Cntr=0.3,0.1

Chan Stop Cuts=-1