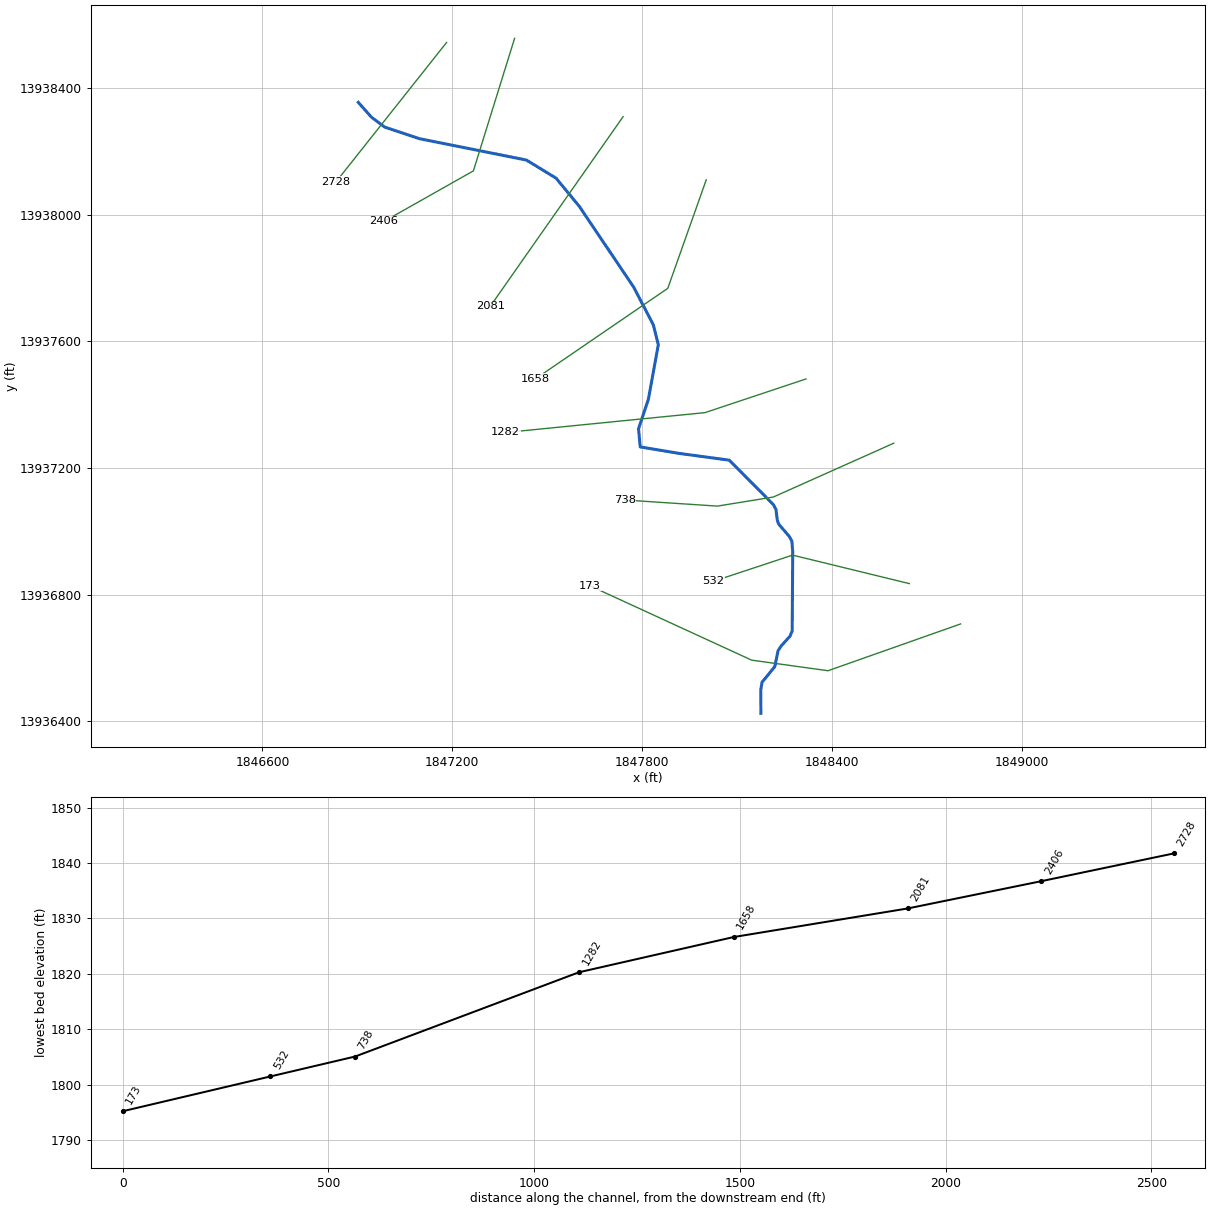
--- Stream0205.prj (project) ---

Proj Title=Stream0205 Base Level Engineering
Current Plan=p01
Default Exp/Contr=0.3,0.1
English Units
Geom File=g01
Flow File=f01
Plan File=p01
BEGIN DESCRIPTION:
Stream0205
END DESCRIPTION:

--- Stream0205.p01 (plan) ---

Plan Title=Multiple Run
Short Identifier=Multiple
Geom File=g01
Flow File=f01
Subcritical Flow
K Sum by GR= 0
Std Step Tol= 0.01
Critical Tol= 0.01
Num of Std Step Trials= 20
Max Error Tol= 0.3
Flow Tol Ratio= 0.001
Split Flow NTrial= 30
Split Flow Tol= 0.02
Split Flow Ratio= 0.02
Log Output Level= 0
Friction Slope Method= 1
Unsteady Friction Slope Method= 2
Unsteady Bridges Friction Slope Method= 1
Parabolic Critical Depth
Global Vel Dist=  1 , 1 , 1
Global Log Level= 0
CheckData=True
Encroach Param= -1, 0, 0, 0
BEGIN DESCRIPTION:
Multiple Run
END DESCRIPTION:

--- Stream0205.f01 (steady flow) ---

Flow Title=Multiple
Number of Profiles=7
Profile Names=10-year,25-year,50-year,1pct_min,100-year,1pct_plu,500-year
River Rch & RM= Stream0205,Reach-1,2728
    1639    2896    4132    2848    5683   11340   10629
Boundary for River Rch & Prof#=Stream0205,Reach-1,1
Up Type=0
Dn Type=3
Dn Slope=0.005
Boundary for River Rch & Prof#=Stream0205,Reach-1,2
Up Type=0
Dn Type=3
Dn Slope=0.005
Boundary for River Rch & Prof#=Stream0205,Reach-1,3
Up Type=0
Dn Type=3
Dn Slope=0.005
Boundary for River Rch & Prof#=Stream0205,Reach-1,4
Up Type=0
Dn Type=3
Dn Slope=0.005
Boundary for River Rch & Prof#=Stream0205,Reach-1,5
Up Type=0
Dn Type=3
Dn Slope=0.005
Boundary for River Rch & Prof#=Stream0205,Reach-1,6
Up Type=0
Dn Type=3
Dn Slope=0.005
Boundary for River Rch & Prof#=Stream0205,Reach-1,7
Up Type=0
Dn Type=3
Dn Slope=0.005

--- Stream0205.g01 (geometry) ---

Geom Title=Existing Conditions

River Reach=Stream0205,Reach-1
Reach XY= 30
      1846902.89     13938355.47      1846944.55     13938308.59
      1846986.22     13938277.34      1847095.59     13938240.88
      1847434.14     13938173.18      1847527.89     13938115.88
      1847600.80     13938027.34      1847772.68     13937772.13
      1847835.18     13937652.34      1847850.80     13937589.84
      1847819.55     13937417.97      1847788.30     13937324.22
      1847793.51     13937266.93      1847918.51     13937246.09
      1848075.00     13937225.00      1848214.24     13937084.69
      1848222.51     13937068.97      1848226.72     13937035.71
      1848231.14     13937022.83      1848264.21     13936984.67
      1848272.76     13936969.07      1848275.46     13936935.19
      1848273.80     13936685.50      1848266.91     13936668.92
      1848239.04     13936638.04      1848229.19     13936623.27
      1848218.91     13936572.81      1848178.63     13936523.50
      1848174.52     13936500.20      1848175.00     13936425.00

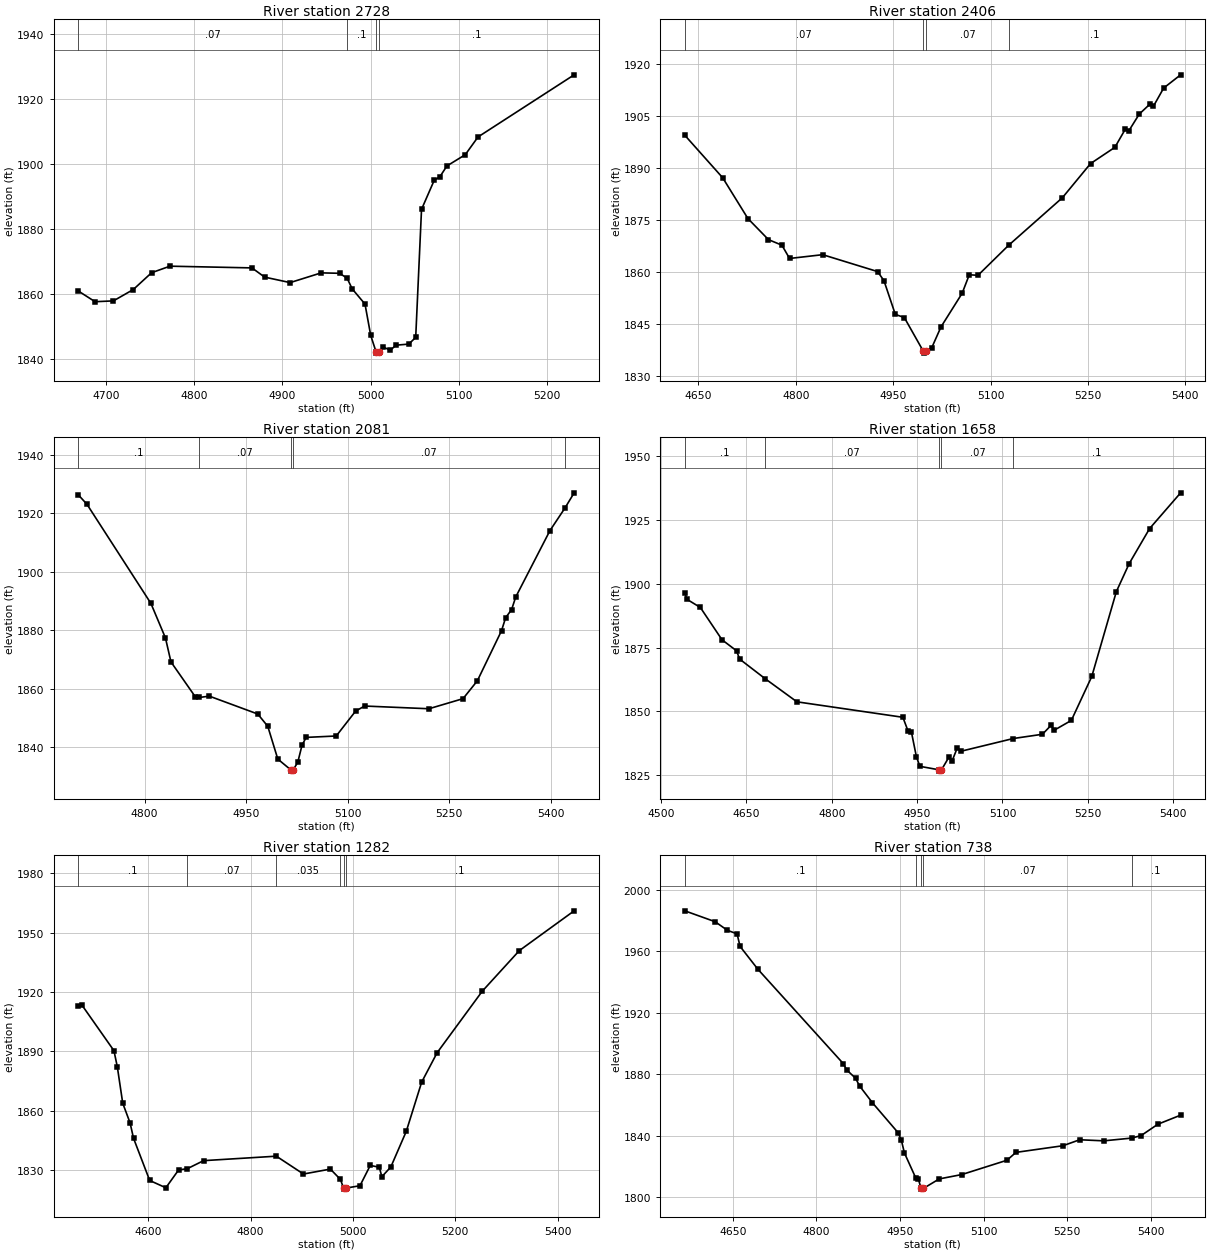
Type RM Length L Ch R = 1,2728,322,322,322
BEGIN DESCRIPTION:
Stream0205 7.0
END DESCRIPTION:
XS GIS Cut Line= 2
      1847181.91     13938544.80      1846832.50     13938104.24
#Sta/Elev= 30
  4668.5 1860.87  4687.5 1857.57  4708.3 1857.83  4730.8 1861.32  4751.6 1866.51
  4772.4 1868.52  4865.4 1867.99  4879.8 1865.15  4908.7 1863.46  4943.9 1866.46
  4964.7 1866.33  4973.3 1864.83  4979.1 1861.52  4993.6 1856.84  5000.1 1847.17
  5006.0 1842.23  5006.2 1841.73  5010.0 1842.23  5014.4 1843.57  5022.4 1842.64
  5028.8 1844.18  5043.2 1844.51  5051.1 1846.57  5057.7 1886.02  5072.1 1894.99
  5078.5 1896.07  5086.5 1899.40  5107.3 1902.87  5121.8 1908.34  5230.8 1927.48
#Mann=4,-1,0
  4668.5    0.07       0  4973.3     0.1       0  5006.0    0.05       0
  5010.0     0.1       0
Bank Sta=5006,5010
Exp/Cntr=0.3,0.1

Type RM Length L Ch R = 1,2406,325,325,325
BEGIN DESCRIPTION:
Stream0205 6.0
END DESCRIPTION:
XS GIS Cut Line= 3
      1847396.73     13938557.77      1847266.53     13938138.96
      1846983.72     13937979.20
#Sta/Elev= 30
  4629.2 1899.53  4687.6 1887.26  4726.4 1875.51  4758.0 1869.44  4778.7 1867.84
  4790.5 1864.01  4841.5 1865.10  4926.0 1860.23  4935.8 1857.63  4953.3 1847.89
  4967.2 1846.97  4996.6 1837.22  4996.9 1836.72  5000.6 1837.22  5009.1 1838.14
  5023.6 1844.26  5056.2 1853.97  5067.2 1859.31  5080.6 1859.15  5127.9 1867.83
  5210.5 1881.51  5253.9 1891.36  5291.4 1896.05  5307.3 1901.24  5313.1 1900.88
  5329.0 1905.65  5344.9 1908.43  5350.6 1907.85  5366.5 1913.14  5392.6 1916.95
#Mann=4,-1,0
  4629.2    0.07       0  4996.6    0.05       0  5000.6    0.07       0
  5127.9     0.1       0
Bank Sta=4996.6,5000.6
Exp/Cntr=0.3,0.1

Type RM Length L Ch R = 1,2081,423,423,423
BEGIN DESCRIPTION:
Stream0205 5.0
END DESCRIPTION:
XS GIS Cut Line= 2
      1847739.64     13938310.43      1847319.55     13937710.61
#Sta/Elev= 30
  4702.0 1926.20  4714.7 1923.01  4809.2 1889.11  4830.7 1877.29  4838.8 1869.12
  4874.6 1857.25  4880.4 1856.96  4895.5 1857.42  4967.0 1851.31  4981.8 1847.11
  4996.6 1835.91  5015.5 1832.29  5015.8 1831.79  5019.5 1832.29  5026.1 1834.82
  5032.4 1840.67  5038.5 1843.32  5082.9 1843.80  5111.5 1852.30  5124.8 1854.04
  5219.8 1853.11  5270.2 1856.56  5291.3 1862.66  5327.0 1879.77  5333.1 1884.23
  5341.9 1887.00  5348.0 1891.30  5398.5 1913.98  5420.6 1921.68  5434.3 1926.91
#Mann=5,-1,0
  4702.0     0.1       0  4880.4    0.07       0  5015.5    0.05       0
  5019.5    0.07       0  5420.6     0.1       0
Bank Sta=5015.5,5019.5
Exp/Cntr=0.3,0.1

Type RM Length L Ch R = 1,1658,376,376,376
BEGIN DESCRIPTION:
Stream0205 4.0
END DESCRIPTION:
XS GIS Cut Line= 3
      1848002.20     13938110.72      1847880.68     13937767.87
      1847461.83     13937481.40
#Sta/Elev= 30
  4541.8 1896.51  4545.5 1893.95  4569.1 1890.74  4607.2 1878.08  4632.7 1873.77
  4638.1 1870.53  4682.8 1862.87  4738.8 1853.78  4925.0 1847.72  4933.9 1842.43
  4940.0 1841.93  4948.8 1832.21  4954.9 1828.51  4988.8 1827.13  4989.0 1826.63
  4992.8 1827.13  5005.7 1832.04  5011.7 1830.74  5020.6 1835.77  5026.7 1834.40
  5119.1 1839.41  5170.2 1841.07  5185.1 1844.52  5191.2 1842.70  5221.0 1846.50
  5256.9 1863.71  5300.1 1896.97  5322.6 1907.92  5358.5 1921.65  5413.0 1935.65
#Mann=5,-1,0
  4541.8     0.1       0  4682.8    0.07       0  4988.8    0.05       0
  4992.8    0.07       0  5119.1     0.1       0
Bank Sta=4988.8,4992.8
Exp/Cntr=0.3,0.1

Type RM Length L Ch R = 1,1282,544,544,544
BEGIN DESCRIPTION:
Stream0205 3.0
END DESCRIPTION:
XS GIS Cut Line= 3
      1848317.33     13937481.58      1847998.33     13937375.24
      1847368.41     13937312.47
#Sta/Elev= 30
  4463.1 1913.12  4469.5 1913.63  4532.7 1890.33  4539.3 1882.19  4549.9 1863.76
  4564.3 1853.73  4571.0 1846.02  4602.6 1824.65  4634.2 1820.96  4659.2 1830.00
  4676.0 1830.59  4708.0 1834.68  4850.2 1836.94  4903.2 1827.91  4955.8 1830.41
  4975.5 1825.18  4981.6 1820.77  4981.8 1820.27  4985.6 1820.77  5013.7 1821.99
  5033.8 1832.26  5051.4 1831.36  5056.5 1826.57  5074.0 1831.48  5104.2 1849.51
  5134.3 1874.42  5164.5 1889.29  5252.8 1920.43  5325.3 1940.98  5432.4 1961.09
#Mann=6,-1,0
  4463.1     0.1       0  4676.0    0.07       0  4850.2   0.035       0
  4975.5     0.1       0  4981.6    0.05       0  4985.6     0.1       0
Bank Sta=4981.6,4985.6
Exp/Cntr=0.3,0.1

Type RM Length L Ch R = 1,738,206,206,206
BEGIN DESCRIPTION:
Stream0205 2.0
END DESCRIPTION:
XS GIS Cut Line= 4
      1848594.74     13937278.65      1848214.17     13937108.52
      1848037.46     13937079.87      1847744.28     13937099.18
#Sta/Elev= 30
  4563.8 1986.50  4618.3 1979.39  4640.2 1973.80  4657.6 1971.49  4663.0 1963.30
  4695.0 1948.39  4848.3 1886.84  4854.2 1882.81  4870.2 1877.36  4877.4 1872.34
  4900.6 1861.32  4946.9 1841.69  4952.5 1836.77  4957.9 1828.62  4978.3 1812.29
  4982.8 1811.68  4987.8 1805.56  4988.1 1805.06  4992.1 1805.56  5020.3 1811.71
  5060.9 1814.57  5141.9 1823.89  5158.0 1829.02  5242.3 1833.35  5272.4 1837.25
  5315.7 1836.54  5365.6 1838.34  5382.6 1839.97  5412.7 1847.38  5453.5 1853.29
#Mann=5,-1,0
  4563.8     0.1       0  4978.3    0.07       0  4987.8    0.05       0
  4992.1    0.07       0  5365.6     0.1       0
Bank Sta=4987.8,4992.1
Exp/Cntr=0.3,0.1

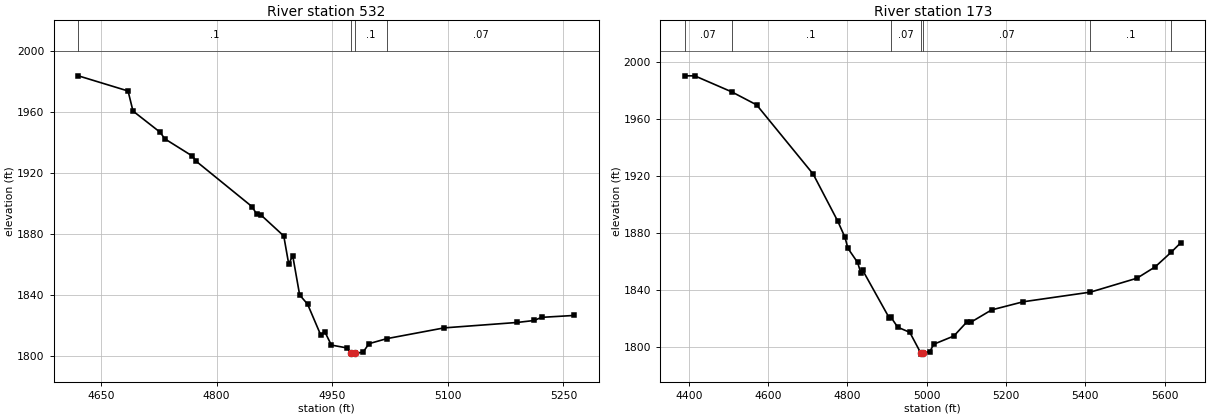
Type RM Length L Ch R = 1,532,359,359,359
BEGIN DESCRIPTION:
Stream0205 1.0
END DESCRIPTION:
XS GIS Cut Line= 3
      1848643.88     13936835.02      1848275.00     13936925.00
      1848024.83     13936842.26
#Sta/Elev= 30
  4620.7 1983.77  4685.2 1973.84  4691.6 1960.71  4726.9 1946.77  4732.8 1942.52
  4768.6 1931.21  4773.9 1927.67  4846.0 1898.09  4851.9 1893.31  4857.1 1892.84
  4887.2 1878.87  4893.6 1860.51  4898.8 1865.95  4907.8 1840.21  4918.1 1834.18
  4935.3 1813.79  4940.4 1816.16  4948.9 1807.39  4969.5 1805.49  4974.8 1801.96
  4975.1 1801.46  4979.1 1801.96  4990.1 1802.78  4997.8 1808.32  5021.0 1811.62
  5095.2 1818.65  5190.0 1822.21  5211.9 1823.49  5221.6 1825.55  5263.9 1826.80
#Mann=4,-1,0
  4620.7     0.1       0  4974.8    0.05       0  4979.1     0.1       0
  5021.0    0.07       0
Bank Sta=4974.8,4979.1
Exp/Cntr=0.3,0.1

Type RM Length L Ch R = 1,173,0,0,0
BEGIN DESCRIPTION:
Stream0205 0.0
END DESCRIPTION:
XS GIS Cut Line= 4
      1848805.75     13936707.53      1848386.91     13936559.74
      1848145.72     13936593.18      1847634.78     13936828.09
#Sta/Elev= 30
  4390.0 1990.41  4415.0 1990.41  4508.4 1979.15  4571.1 1970.03  4713.7 1921.45
  4775.6 1888.46  4793.8 1877.13  4801.2 1869.43  4825.6 1859.51  4834.1 1851.84
  4838.6 1853.93  4905.3 1820.62  4909.0 1821.29  4926.9 1814.05  4957.2 1810.48
  4985.4 1795.68  4985.6 1795.18  4989.7 1795.68  5007.7 1796.98  5017.8 1802.14
  5068.3 1807.89  5100.5 1817.58  5111.5 1817.62  5163.4 1826.19  5243.5 1831.93
  5412.7 1838.68  5530.0 1848.45  5576.0 1856.43  5615.8 1866.55  5640.0 1873.20
#Mann=7,-1,0
  4390.0    0.07       0  4508.4     0.1       0  4909.0    0.07       0
  4985.4    0.05       0  4989.7    0.07       0  5412.7     0.1       0
  5615.8    0.07       0
Bank Sta=4985.4,4989.7
Exp/Cntr=0.3,0.1

Chan Stop Cuts=-1