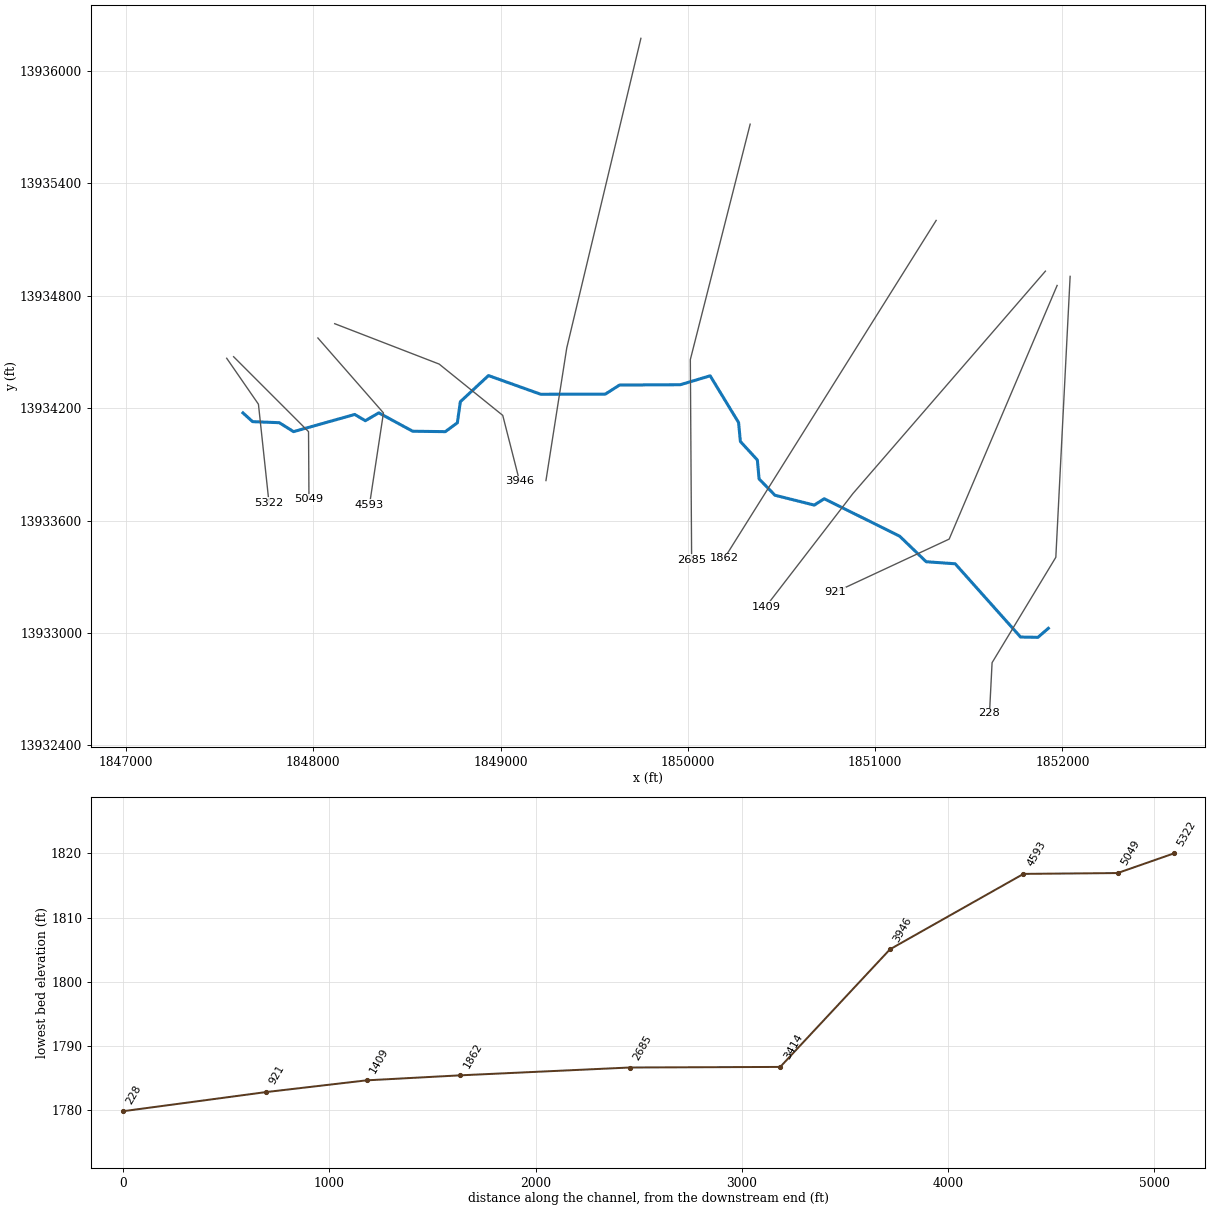
--- Stream0206.prj (project) ---

Proj Title=Stream0206 Base Level Engineering
Current Plan=p01
Default Exp/Contr=0.3,0.1
English Units
Geom File=g01
Flow File=f01
Plan File=p01
Y Axis Title=Elevation
X Axis Title(PF)=Main Channel Distance
X Axis Title(XS)=Station
BEGIN DESCRIPTION:
Stream0206
END DESCRIPTION:
DSS Export Rating Curves= 0
DSS Export Rating Curve Sorted= 0
DSS Export Volume Flow Curves= 0
DXF OffsetX= 0
DXF OffsetY= 0
DXF ScaleX= 1
DXF ScaleY= 10

--- Stream0206.p01 (plan) ---

Plan Title=Multiple Run
Short Identifier=Multiple
Geom File=g01
Flow File=f01
Subcritical Flow
K Sum by GR= 0
Std Step Tol= 0.01
Critical Tol= 0.01
Num of Std Step Trials= 20
Max Error Tol= 0.3
Flow Tol Ratio= 0.001
Split Flow NTrial= 30
Split Flow Tol= 0.02
Split Flow Ratio= 0.02
Log Output Level= 0
Friction Slope Method= 1
Unsteady Friction Slope Method= 2
Unsteady Bridges Friction Slope Method= 1
Parabolic Critical Depth
Global Vel Dist=  1 , 1 , 1
Global Log Level= 0
CheckData=True
Encroach Param= -1, 0, 0, 0
BEGIN DESCRIPTION:
Multiple Run
END DESCRIPTION:

--- Stream0206.f01 (steady flow) ---

Flow Title=Multiple
Number of Profiles=7
Profile Names=10-year,25-year,50-year,1pct_min,100-year,1pct_plu,500-year
River Rch & RM= Stream0206,Reach-1,5322
    1885    3342    4779    3298    6580   13128   12336
Boundary for River Rch & Prof#=Stream0206,Reach-1,1
Up Type=0
Dn Type=3
Dn Slope=0.005
Boundary for River Rch & Prof#=Stream0206,Reach-1,2
Up Type=0
Dn Type=3
Dn Slope=0.005
Boundary for River Rch & Prof#=Stream0206,Reach-1,3
Up Type=0
Dn Type=3
Dn Slope=0.005
Boundary for River Rch & Prof#=Stream0206,Reach-1,4
Up Type=0
Dn Type=3
Dn Slope=0.005
Boundary for River Rch & Prof#=Stream0206,Reach-1,5
Up Type=0
Dn Type=3
Dn Slope=0.005
Boundary for River Rch & Prof#=Stream0206,Reach-1,6
Up Type=0
Dn Type=3
Dn Slope=0.005
Boundary for River Rch & Prof#=Stream0206,Reach-1,7
Up Type=0
Dn Type=3
Dn Slope=0.005

--- Stream0206.g01 (geometry) ---

Geom Title=Existing Conditions
Program Version=4.10

River Reach=Stream0206      ,Reach-1
Reach XY= 30
        1847625.       13934175.      1847676.37      13934128.3
      1847819.06     13934122.73      1847895.04     13934075.05
      1848221.78     13934166.73      1848278.23     13934133.32
      1848349.96     13934175.33      1848530.93     13934077.24
      1848705.13     13934074.91      1848769.59     13934122.29
      1848785.52     13934234.78      1848935.62      13934374.4
      1849214.81     13934274.55      1849559.78     13934275.52
       1849635.5     13934323.78      1849959.78     13934325.52
      1850119.29     13934373.11      1850271.17     13934123.41
      1850280.54     13934022.58      1850371.37      13933923.5
      1850380.52     13933822.56      1850465.18     13933735.47
       1850675.1      13933682.8      1850728.23     13933716.76
      1851131.06     13933516.86      1851272.55     13933380.47
      1851427.45     13933369.53      1851776.47     13932978.44
      1851869.16     13932976.77        1851925.       13933025.

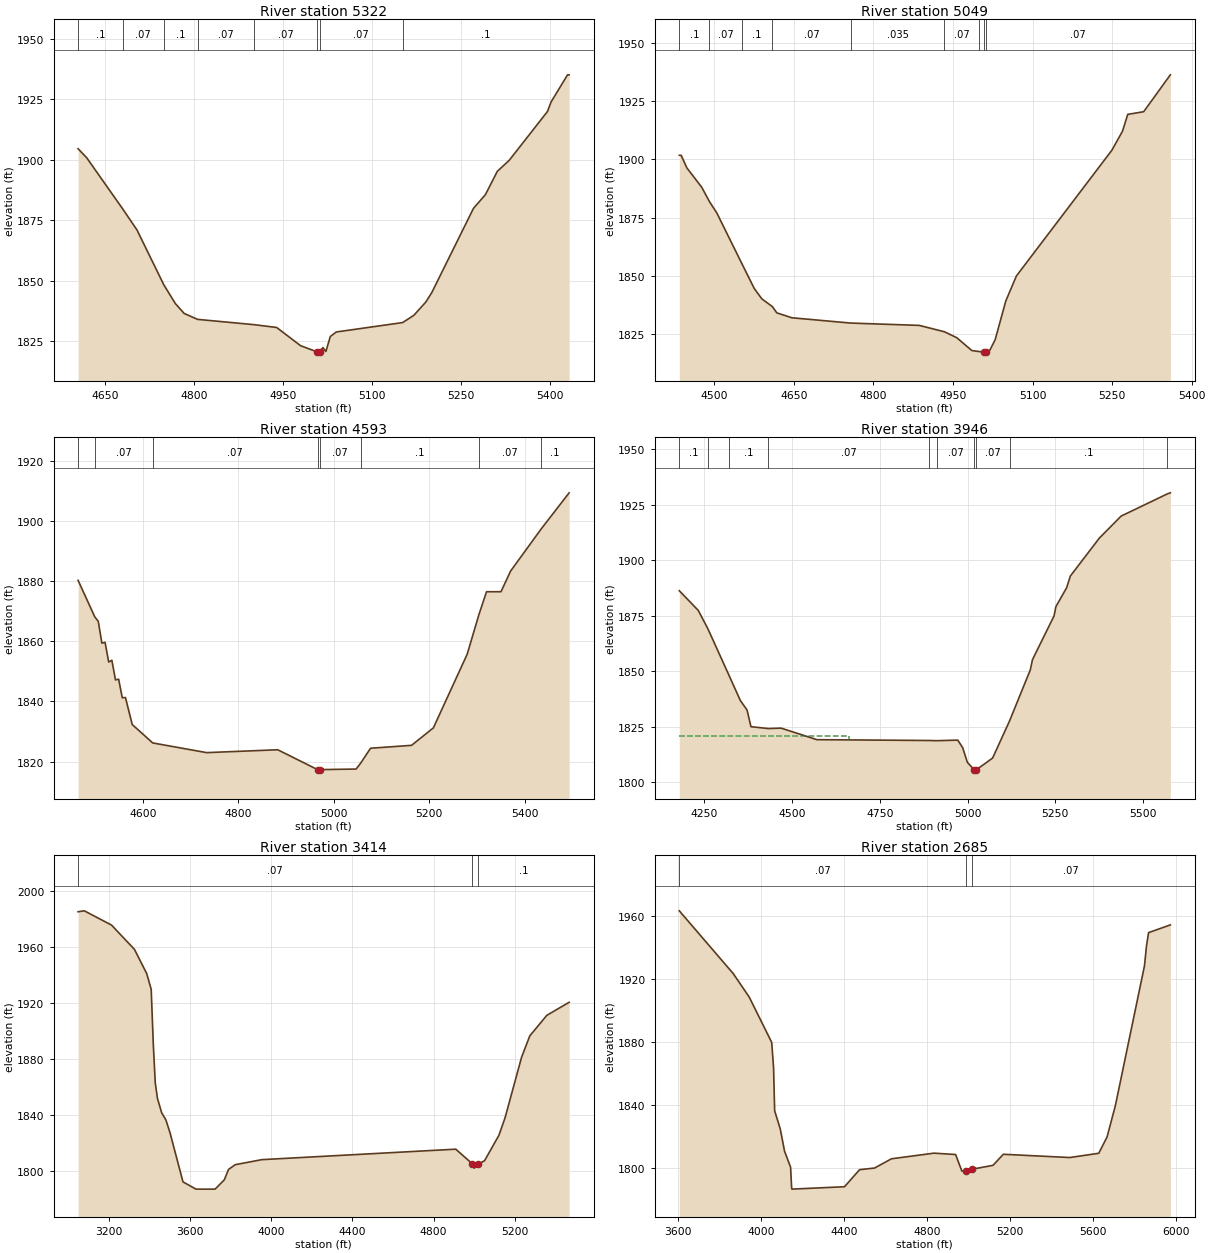
Type RM Length L Ch R = 1 ,5322    ,273,273,273
BEGIN DESCRIPTION:
Stream0206 4.0
END DESCRIPTION:
XS GIS Cut Line= 3
      1847538.08     13934466.79      1847707.53     13934221.45
      1847763.98     13933694.64
#Sta/Elev= 30
  4604.5 1904.56  4618.8 1900.91  4679.6 1879.71  4703.9 1870.92  4748.9 1848.33
  4768.5  1840.5  4783.4  1836.4    4806 1833.96    4901 1831.77  4939.3 1830.61
  4979.6 1823.08  5007.7 1820.49  5007.9 1819.99  5011.8 1820.49  5017.3 1822.29
  5022.3 1820.66  5029.8 1826.87  5039.9 1828.74  5151.8 1832.64  5170.6 1835.63
  5190.8 1841.12  5200.8 1844.99  5271.2 1879.89  5291.3 1885.56  5311.4 1895.21
  5331.6 1899.81    5396 1919.99    5402 1923.89  5429.8 1935.15  5432.5 1935.15
#Mann= 8 ,-1 , 0
  4604.5      .1       0  4679.6     .07       0  4748.9      .1       0
    4806     .07       0    4901     .07       0  5007.7     .05       0
  5011.8     .07       0  5151.8      .1       0
Bank Sta=5007.7,5011.8
XS Rating Curve= 0 ,0
Exp/Cntr=0.3,0.1

Type RM Length L Ch R = 1 ,5049    ,456,456,456
BEGIN DESCRIPTION:
Stream0206 3.0
END DESCRIPTION:
XS GIS Cut Line= 3
      1847574.97     13934475.03        1847975.       13934075.
      1847977.32     13933714.74
#Sta/Elev= 30
  4433.8 1901.75  4437.4 1901.75    4448 1896.37  4476.3 1887.98  4490.6 1881.92
  4504.6 1877.01  4551.1 1855.62  4575.3 1844.58  4589.4 1840.22  4609.4 1836.85
  4617.7 1834.19    4646 1832.09  4756.7 1829.82  4886.4 1828.82  4933.9 1826.08
  4957.1 1823.54  4985.4 1818.05  4998.3 1817.63  5007.5 1817.43  5007.7 1816.93
  5011.6 1817.43  5019.5 1818.19  5029.5 1822.72  5049.5  1839.3  5069.5 1850.01
  5249.5 1903.91  5269.5 1912.04  5279.5  1919.3  5309.5 1920.43  5359.8 1936.25
#Mann= 9 ,-1 , 0
  4433.8      .1       0  4490.6     .07       0  4551.1      .1       0
  4609.4     .07       0  4756.7    .035       0  4933.9     .07       0
  4998.3     .07       0  5007.5     .05       0  5011.6     .07       0
Bank Sta=5007.5,5011.6
XS Rating Curve= 0 ,0
Exp/Cntr=0.3,0.1

Type RM Length L Ch R = 1 ,4593    ,647,647,647
BEGIN DESCRIPTION:
Stream0206 2.0
END DESCRIPTION:
XS GIS Cut Line= 3
        1848025.       13934575.        1848375.       13934175.
      1848300.43     13933683.94
#Sta/Elev= 30
  4464.5 1880.23  4499.4  1868.1  4506.7  1866.6  4514.3 1859.34    4521 1859.61
  4528.6 1853.06  4535.2 1853.65  4542.8 1847.13  4549.4 1847.37    4557 1841.19
  4563.7 1841.25  4577.9 1832.28  4620.8 1826.17  4733.6 1822.95  4882.6  1823.9
  4965.9  1817.3  4966.2  1816.8  4970.1  1817.3  5046.6 1817.49  5056.2 1819.46
  5076.9 1824.41  5162.7 1825.37  5208.4 1831.17  5279.2 1855.65  5303.8 1868.83
  5319.7 1876.43    5350 1876.44  5370.2 1883.32  5434.4 1897.35  5492.7 1909.31
#Mann= 8 ,-1 , 0
  4464.5      .1       0  4499.4     .07       0  4620.8     .07       0
  4965.9     .05       0  4970.1     .07       0  5056.2      .1       0
  5303.8     .07       0  5434.4      .1       0
Bank Sta=4965.9,4970.1
XS Rating Curve= 0 ,0
Exp/Cntr=0.3,0.1

Type RM Length L Ch R = 1 ,3946    ,532,532,532
BEGIN DESCRIPTION:
Stream0206 1.0
END DESCRIPTION:
XS GIS Cut Line= 4
      1848114.73     13934651.35       1848672.4     13934435.74
      1849011.92     13934161.79      1849101.97     13933809.27
#Sta/Elev= 30
  4179.4 1886.33  4233.3 1877.47  4260.8  1869.2  4322.1  1847.8  4353.1 1836.91
  4372.3 1832.59  4383.4 1825.08  4432.5 1824.24  4469.2 1824.43  4571.2 1819.23
  4891.6 1818.86  4912.3 1818.77  4972.3 1819.03  4986.2  1815.6  4999.5 1809.04
  5019.5 1805.56  5019.8 1805.06  5024.2 1805.56  5071.4 1810.95  5119.6 1827.65
  5178.6 1850.62    5185 1855.32  5246.3 1874.96  5251.5 1879.14    5282 1887.63
  5292.8 1892.96  5375.4 1910.06  5437.3 1919.95    5569 1929.96  5577.4 1930.43
#Mann= 10 ,-1 , 0
  4179.4      .1       0  4260.8     .05       0  4322.1      .1       0
  4432.5     .07       0  4891.6    .035       0  4912.3     .07       0
  5019.5     .05       0  5024.2     .07       0  5119.6      .1       0
    5569     .07       0
#XS Ineff= 2 , 0
         4663.57 1820.98
Permanent Ineff=
       F       F
Bank Sta=5019.5,5024.2
XS Rating Curve= 0 ,0
Exp/Cntr=0.3,0.1

Type RM Length L Ch R = 1 ,3414    ,729,729,729
BEGIN DESCRIPTION:
Stream0206 0.0
END DESCRIPTION:
XS GIS Cut Line= 3
      1849749.53      13936174.9      1849353.71     13934522.16
      1849242.59      13933813.8
#Sta/Elev= 30
  3050.3 1985.09    3081 1985.75  3214.7 1975.57  3327.8 1958.17  3388.1 1940.84
  3410.1 1929.63  3420.4 1890.43  3430.1 1862.68  3440.9  1851.6  3461.5 1841.39
  3482.4 1836.25  3502.6  1827.1  3566.5 1791.92  3630.4 1786.74  3724.5 1786.74
    3770 1793.43  3790.6 1800.82  3823.8 1804.23  3955.1 1807.83  4908.9 1815.31
  4989.8 1804.94    5000 1801.69  5020.2 1804.63  5050.6 1807.07  5121.4 1825.28
  5151.8 1837.94  5232.8 1881.07  5273.3 1896.35  5356.9 1911.01  5466.8 1920.35
#Mann= 3 ,-1 , 0
  3050.3     .07       0  4989.8     .05       0  5020.2      .1       0
#Block Obstruct= 2 , 0
         4887.93 1814.61
Bank Sta=4989.8,5020.2
XS Rating Curve= 0 ,0
Exp/Cntr=0.3,0.1

Type RM Length L Ch R = 1 ,2685    ,823,823,823
BEGIN DESCRIPTION:
Stream0206 0.1
END DESCRIPTION:
XS GIS Cut Line= 3
      1850332.88     13935716.62      1850013.43     13934459.66
      1850020.38      13933390.2
#Sta/Elev= 30
  3606.5 1963.54  3866.5 1923.64  3943.2 1908.79  4051.8 1879.93  4060.9 1863.54
    4066 1836.47  4093.1 1824.86  4113.8 1810.72  4142.8 1800.61  4147.7 1787.85
  4149.2 1786.65  4402.7 1788.17  4475.4 1799.02    4547 1800.03  4628.8 1805.92
  4833.5 1809.51  4938.1 1808.65  4968.1 1798.15  4988.1  1798.4  5018.1 1799.34
  5118.1 1801.76  5168.1  1808.8  5488.1 1806.73  5628.1 1809.44  5668.1 1819.85
  5708.1 1839.81  5848.1 1928.46  5858.1  1941.4  5868.1 1949.69  5972.9 1954.59
#Mann= 3 ,-1 , 0
  3606.5     .07       0  4988.1     .05       0  5018.1     .07       0
#Block Obstruct= 2 , 0
         4832.26 1809.04
Bank Sta=4988.1,5018.1
XS Rating Curve= 0 ,0
Exp/Cntr=0.3,0.1

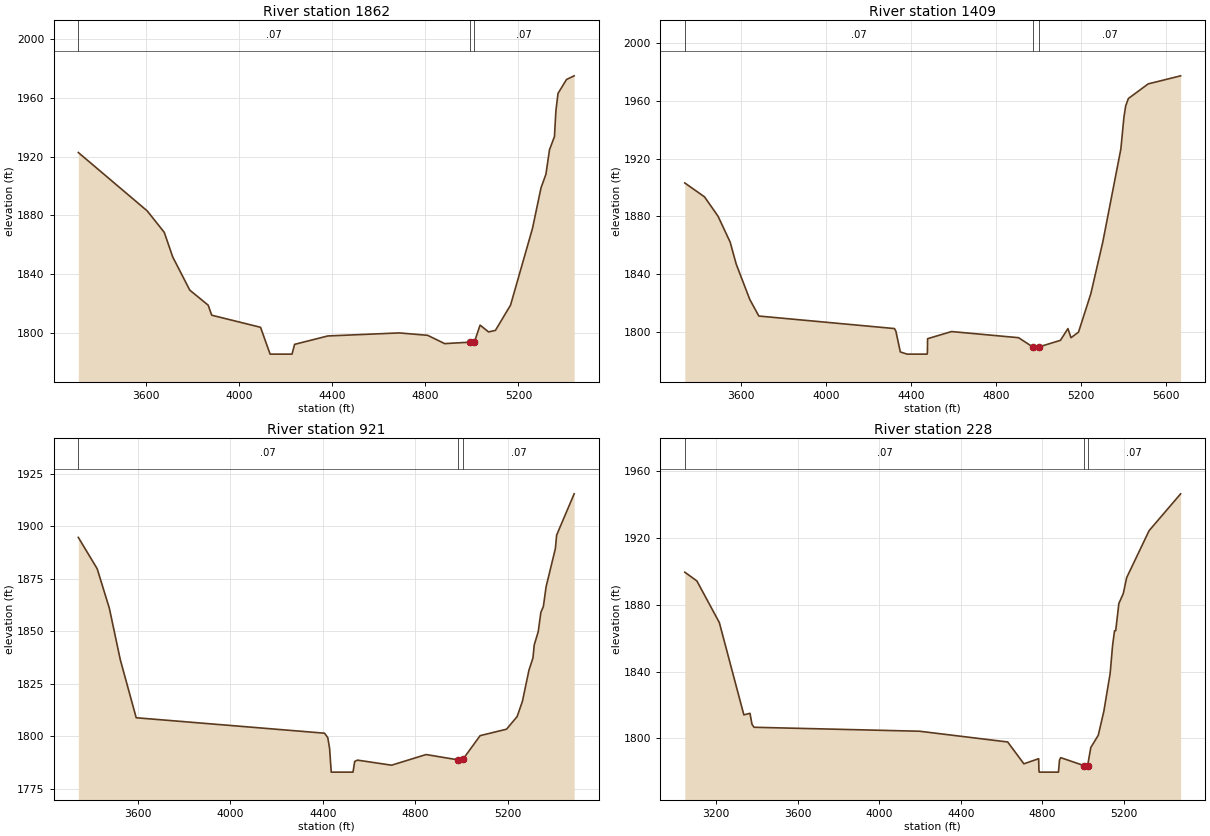
Type RM Length L Ch R = 1 ,1862    ,453,453,453
BEGIN DESCRIPTION:
Stream0206 0.2
END DESCRIPTION:
XS GIS Cut Line= 2
      1851325.94     13935202.74      1850194.87     13933398.57
#Sta/Elev= 30
  3310.1 1922.73    3606 1882.97  3679.1 1868.39  3715.6 1851.58  3788.7 1829.03
  3867.7 1818.78    3883 1811.94  4092.7  1803.7  4133.7 1785.43  4227.9 1785.43
  4238.9 1792.09  4381.5  1797.8  4688.3 1799.88  4810.4 1798.23  4883.5 1792.59
  4993.1 1793.58 5010.63 1793.49  5035.5 1805.17    5072 1800.55  5101.4  1801.6
  5166.3  1818.8  5260.6 1871.09  5297.1 1898.63  5318.3 1907.99  5333.6  1924.6
  5354.9  1933.6  5361.1 1951.16  5370.2 1962.97  5406.7 1972.47  5439.5 1974.96
#Mann= 3 ,-1 , 0
  3310.1     .07       0  4993.1     .05       0 5010.63     .07       0
#Block Obstruct= 2 , 0
         4633.81 1799.71
Bank Sta=4993.1,5010.63
XS Rating Curve= 0 ,0
Exp/Cntr=0.3,0.1

Type RM Length L Ch R = 1 ,1409    ,488,488,488
BEGIN DESCRIPTION:
Stream0206 0.3
END DESCRIPTION:
XS GIS Cut Line= 3
      1851909.25     13934931.87      1850881.49     13933744.39
      1850416.18     13933140.18
#Sta/Elev= 30
    3336  1903.1  3428.8 1893.47  3492.4 1880.08  3549.4  1862.2  3577.9 1846.95
  3641.6 1822.56  3684.3 1811.01  4322.6 1802.34  4329.2 1800.53  4350.2 1786.17
  4381.9 1784.65  4476.1 1784.65  4477.6 1785.85  4478.4 1795.33  4591.4 1800.27
  4906.5 1796.02  4974.8 1789.49  5003.8 1789.71  5103.5 1794.19  5138.8 1802.31
  5153.3 1796.01  5188.6 1799.86  5246.5  1826.4  5302.8 1862.17  5387.9 1926.63
  5402.4 1948.68  5410.6 1956.47  5423.3 1961.53  5516.6 1971.64  5669.1 1977.22
#Mann= 3 ,-1 , 0
    3336     .07       0  4974.8     .05       0  5003.8     .07       0
#Block Obstruct= 2 , 0
         4590.97 1800.49
Bank Sta=4974.8,5003.8
XS Rating Curve= 0 ,0
Exp/Cntr=0.3,0.1

Type RM Length L Ch R = 1 ,921     ,693,693,693
BEGIN DESCRIPTION:
Stream0206 0.5
END DESCRIPTION:
XS GIS Cut Line= 3
      1851971.77     13934855.51      1851395.38     13933501.33
      1850784.29     13933216.62
#Sta/Elev= 30
  3342.3 1894.77  3423.9 1879.84  3476.6 1860.97  3523.9 1836.45  3592.8 1808.76
  4407.9 1801.39  4421.7 1799.32  4429.7 1794.23  4436.9 1782.82  4531.1 1782.82
  4538.4 1787.92  4550.8 1788.54    4698 1786.13  4847.6 1791.21  4984.2  1788.7
  5007.1 1788.98  5081.2 1800.22  5195.6  1803.3  5241.3 1809.31  5264.2 1816.55
  5292.6 1831.46  5309.9 1837.27  5315.4 1843.48  5332.8 1849.84    5344 1858.99
    5355 1861.84  5366.7 1871.22  5406.9 1889.45  5412.4 1895.88  5488.2 1915.57
#Mann= 3 ,-1 , 0
  3342.3     .07       0  4984.2     .05       0  5007.1     .07       0
#Block Obstruct= 2 , 0
         4848.65 1791.21
Bank Sta=4984.2,5007.1
XS Rating Curve= 0 ,0
Exp/Cntr=0.3,0.1

Type RM Length L Ch R = 1 ,228     ,0,0,0
BEGIN DESCRIPTION:
Stream0206 0.4
END DESCRIPTION:
XS GIS Cut Line= 4
      1852041.21     13934904.11      1851964.82     13933404.11
      1851624.54     13932841.61      1851610.66     13932570.82
#Sta/Elev= 30
  3046.8 1899.52    3106 1894.28  3216.1 1869.38  3336.3 1814.12  3366.3 1815.04
  3376.3  1808.4  3386.3 1806.69  4197.4 1804.32  4629.5 1797.89    4709 1784.82
  4781.4 1787.88  4782.7 1781.04  4784.2 1779.84  4878.4 1779.84  4883.6 1787.05
  4889.5 1788.51  5005.9 1783.65  5021.4 1783.72  5036.9 1794.55  5073.6  1801.9
  5100.9 1816.24  5131.9 1838.95  5143.8 1855.67  5153.3 1864.48  5159.1 1864.49
  5174.6 1880.83    5196 1886.63  5212.8 1896.26  5322.9  1924.4  5477.3 1946.42
#Mann= 3 ,-1 , 0
  3046.8     .07       0  5005.9     .05       0  5021.4     .07       0
#Block Obstruct= 2 , 0
         4889.03  1788.5
Bank Sta=5005.9,5021.4
XS Rating Curve= 0 ,0
Exp/Cntr=0.3,0.1

Chan Stop Cuts=-1
Use User Specified Reach Order=0
Composite Channel Slope=5