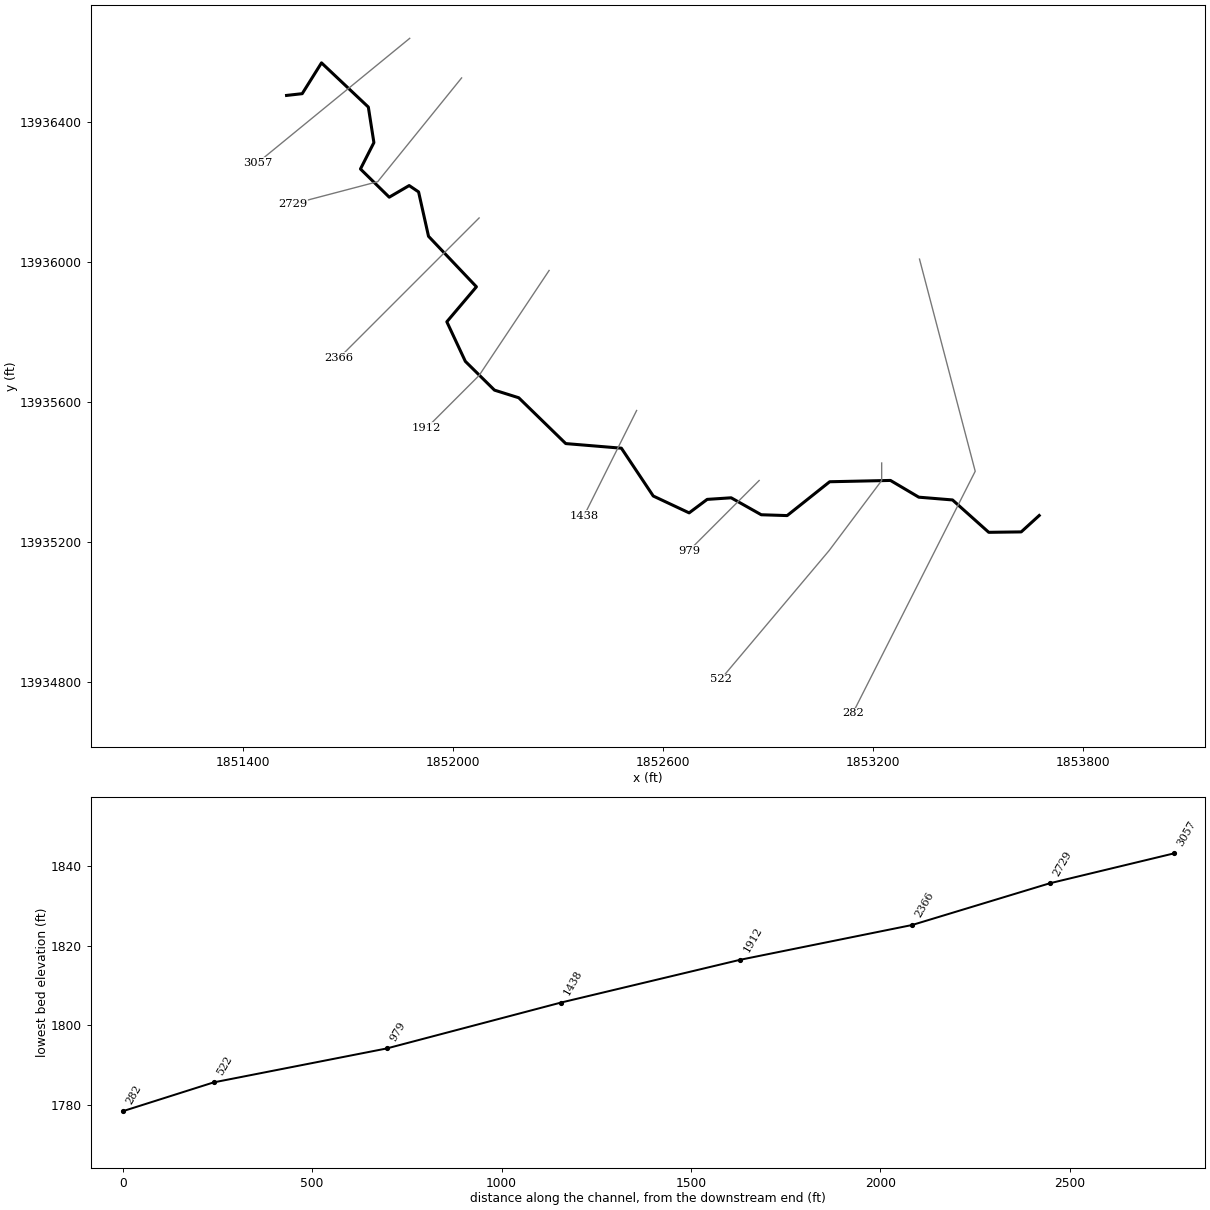
--- Stream0207.prj (project) ---

Proj Title=Stream0207 Base Level Engineering
Current Plan=p01
Default Exp/Contr=0.3,0.1
English Units
Geom File=g01
Flow File=f01
Plan File=p01
Y Axis Title=Elevation
X Axis Title(PF)=Main Channel Distance
X Axis Title(XS)=Station
BEGIN DESCRIPTION:
Stream0207
END DESCRIPTION:
DSS Export Rating Curves= 0
DSS Export Rating Curve Sorted= 0
DSS Export Volume Flow Curves= 0
DXF OffsetX= 0
DXF OffsetY= 0
DXF ScaleX= 1
DXF ScaleY= 10

--- Stream0207.p01 (plan) ---

Plan Title=Multiple Run
Short Identifier=Multiple
Geom File=g01
Flow File=f01
Subcritical Flow
K Sum by GR= 0
Std Step Tol= 0.01
Critical Tol= 0.01
Num of Std Step Trials= 20
Max Error Tol= 0.3
Flow Tol Ratio= 0.001
Split Flow NTrial= 30
Split Flow Tol= 0.02
Split Flow Ratio= 0.02
Log Output Level= 0
Friction Slope Method= 1
Unsteady Friction Slope Method= 2
Unsteady Bridges Friction Slope Method= 1
Parabolic Critical Depth
Global Vel Dist=  1 , 1 , 1
Global Log Level= 0
CheckData=True
Encroach Param= -1, 0, 0, 0
BEGIN DESCRIPTION:
Multiple Run
END DESCRIPTION:

--- Stream0207.f01 (steady flow) ---

Flow Title=Multiple
Program Version=4.10
Number of Profiles= 7
Profile Names=10-year,25-year,50-year,1pct_min,100-year,1pct_plu,500-year
River Rch & RM=Stream0207,Reach-1         ,3057
     748    1260    1742    1168    2330    4648    4111
Boundary for River Rch & Prof#=Stream0207,Reach-1         , 1
Up Type= 0
Dn Type= 3
Dn Slope=0.02
Boundary for River Rch & Prof#=Stream0207,Reach-1         , 2
Up Type= 0
Dn Type= 3
Dn Slope=0.02
Boundary for River Rch & Prof#=Stream0207,Reach-1         , 3
Up Type= 0
Dn Type= 3
Dn Slope=0.02
Boundary for River Rch & Prof#=Stream0207,Reach-1         , 4
Up Type= 0
Dn Type= 3
Dn Slope=0.02
Boundary for River Rch & Prof#=Stream0207,Reach-1         , 5
Up Type= 0
Dn Type= 3
Dn Slope=0.02
Boundary for River Rch & Prof#=Stream0207,Reach-1         , 6
Up Type= 0
Dn Type= 3
Dn Slope=0.02
Boundary for River Rch & Prof#=Stream0207,Reach-1         , 7
Up Type= 0
Dn Type= 3
Dn Slope=0.02
DSS Import GetInterval= 0
DSS Import GetPeak= 0
DSS Import FillOption= 0

--- Stream0207.g01 (geometry) ---

Geom Title=Existing Conditions
Program Version=4.10

River Reach=Stream0207      ,Reach-1
Reach XY= 30
        1851525.       13936475.      1851569.67     13936480.01
       1851624.8     13936568.03       1851758.6     13936441.76
      1851774.48     13936340.22       1851736.1     13936264.89
       1851818.3     13936184.31      1851875.24     13936217.54
      1851902.12     13936199.41      1851930.53     13936072.58
      1852067.39     13935928.33       1851982.8     13935828.41
      1852035.74      13935715.3      1852118.93     13935633.15
      1852188.21     13935611.37      1852322.55     13935480.47
      1852481.47      13935467.3      1852572.46      13935330.7
      1852674.99     13935282.53       1852726.5     13935321.06
      1852795.04     13935325.58      1852880.98     13935277.17
      1852954.95     13935274.79      1853076.47     13935371.45
      1853250.08      13935375.2      1853330.98     13935327.36
      1853427.42     13935319.46      1853530.88     13935226.96
      1853623.59     13935228.18        1853675.       13935275.

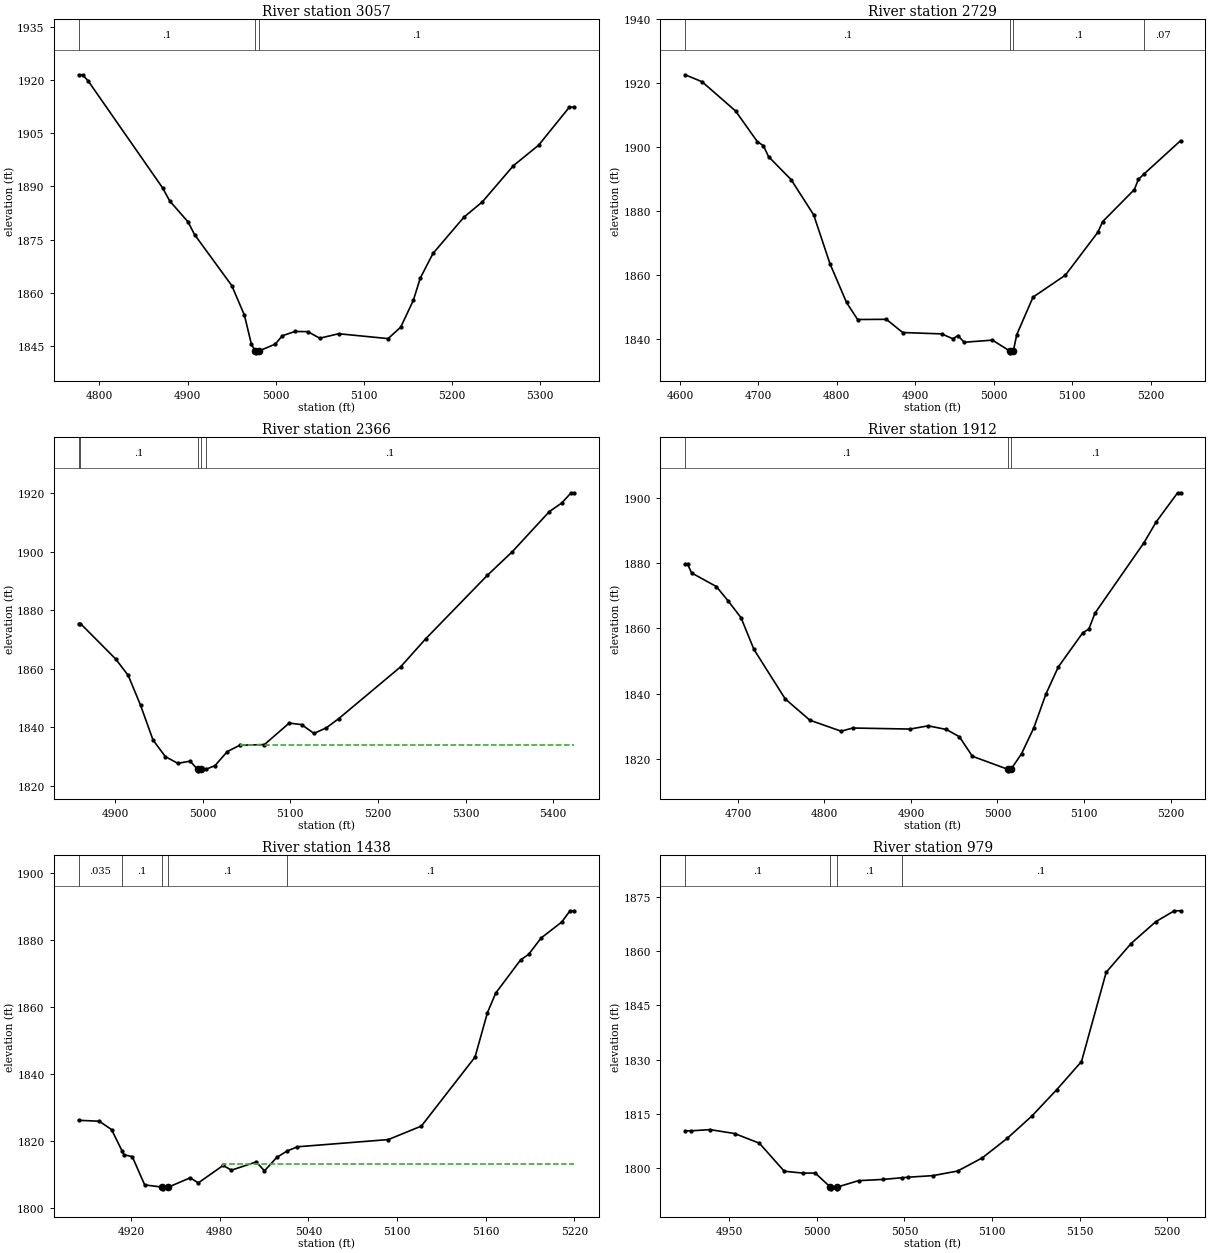
Type RM Length L Ch R = 1 ,3057    ,328,328,328
BEGIN DESCRIPTION:
Stream0207 7.0
END DESCRIPTION:
XS GIS Cut Line= 2
      1851876.78      13936638.1      1851441.63     13936282.13
#Sta/Elev= 30
  4776.4 1921.45  4780.8 1921.45  4787.2 1919.73  4871.9  1889.5  4879.8 1885.88
  4900.6 1879.99  4907.9 1876.43  4950.1 1862.08  4964.5 1853.73  4972.4 1845.54
  4976.8 1843.62  4977.1 1843.12  4980.8 1843.62  4999.6 1845.59  5007.5 1847.94
  5021.9 1849.14  5036.3 1849.09    5050 1847.24  5071.4  1848.5  5127.5 1847.13
  5141.8 1850.35  5156.1  1857.9    5164 1864.17  5178.4 1871.11  5213.6 1881.36
  5234.4 1885.64  5269.6 1895.83  5298.3 1901.63  5333.2 1912.34  5338.6 1912.34
#Mann= 3 ,-1 , 0
  4776.4      .1       0  4976.8     .05       0  4980.8      .1       0
#XS Ineff= 2 , 0
                         5028.77         1848.79
Permanent Ineff=
       F       F
Bank Sta=4976.8,4980.8
XS Rating Curve= 0 ,0
Exp/Cntr=0.3,0.1

Type RM Length L Ch R = 1 ,2729    ,363,363,363
BEGIN DESCRIPTION:
Stream0207 6.0
END DESCRIPTION:
XS GIS Cut Line= 3
      1852025.02     13936525.02      1851785.35     13936228.63
      1851542.94     13936164.97
#Sta/Elev= 30
  4606.6 1922.63  4628.2 1920.46  4670.9 1911.32  4698.6 1901.74  4706.5 1900.42
    4713 1897.01  4741.7 1889.84  4770.5 1878.82  4791.3 1863.51  4812.4 1851.39
  4826.5 1846.05  4863.2 1846.11    4884 1841.98  4933.6 1841.55    4948 1840.03
  4954.4    1841  4962.4 1838.93  4998.5  1839.6    5021 1836.12  5021.3 1835.62
    5025 1836.12  5029.5 1841.35  5050.2 1853.05  5091.5 1859.94  5132.9 1873.37
  5138.9 1876.66  5179.3 1886.69  5184.6 1889.93    5192 1891.65  5238.4 1902.03
#Mann= 4 ,-1 , 0
  4606.6      .1       0    5021     .05       0    5025      .1       0
    5192     .07       0
#XS Ineff= 2 , 0
         4933.33 1841.55
Permanent Ineff=
       F       F
Bank Sta=5021,5025
XS Rating Curve= 0 ,0
Exp/Cntr=0.3,0.1

Type RM Length L Ch R = 1 ,2366    ,454,454,454
BEGIN DESCRIPTION:
Stream0207 5.0
END DESCRIPTION:
XS GIS Cut Line= 3
      1852075.01     13936125.01        1851975.       13936025.
        1851675.       13935725.
#Sta/Elev= 30
  4858.3 1875.44  4860.4 1875.44  4900.7 1863.31  4914.9 1857.74    4929 1847.55
  4943.2 1835.71  4957.3 1830.02  4971.5 1827.74  4985.6 1828.47  4994.2 1825.67
  4994.5 1825.17  4998.2 1825.67  5004.1 1825.77  5013.9 1826.93    5028 1831.74
  5042.2  1833.9  5070.4 1834.14  5098.7 1841.47  5112.9 1840.95    5127 1837.93
  5141.2 1839.88  5155.3 1843.01    5226  1860.7  5254.3 1870.18    5325 1891.94
  5353.3 1899.94  5395.7 1913.67  5409.9 1916.61  5420.5 1920.08    5424 1920.08
#Mann= 5 ,-1 , 0
  4858.3      .1       0  4860.4      .1       0  4994.2     .05       0
  4998.2      .1       0  5004.1      .1       0
#XS Ineff= 2 , 0
                         5042.31         1833.94
Permanent Ineff=
       F       F
Bank Sta=4994.2,4998.2
XS Rating Curve= 0 ,0
Exp/Cntr=0.3,0.1

Type RM Length L Ch R = 1 ,1912    ,474,474,474
BEGIN DESCRIPTION:
Stream0207 4.0
END DESCRIPTION:
XS GIS Cut Line= 3
      1852275.01     13935975.01        1852075.       13935675.
        1851925.       13935525.
#Sta/Elev= 30
    4639 1879.59    4642 1879.59  4646.5    1877  4675.1 1872.83  4688.6 1868.48
  4703.6 1863.31  4718.6 1853.57  4754.7 1838.45  4783.2 1831.94  4819.3 1828.58
  4832.8 1829.55  4898.9 1829.23  4919.9 1830.22    4941  1829.1    4956 1826.88
    4971 1820.91  5011.7 1816.95    5012 1816.45  5015.7 1816.95  5027.8 1821.67
    5042  1829.6  5056.1    1840  5070.3 1848.23  5098.6 1858.69  5105.6 1859.81
  5112.7 1864.69  5169.3 1886.22  5183.4 1892.58  5208.2 1901.51  5211.7 1901.51
#Mann= 3 ,-1 , 0
    4639      .1       0  5011.7     .05       0  5015.7      .1       0
Bank Sta=5011.7,5015.7
XS Rating Curve= 0 ,0
Exp/Cntr=0.3,0.1

Type RM Length L Ch R = 1 ,1438    ,459,459,459
BEGIN DESCRIPTION:
Stream0207 3.0
END DESCRIPTION:
XS GIS Cut Line= 3
      1852524.99     13935574.98        1852475.       13935475.
        1852375.     13935274.99
#Sta/Elev= 30
  4884.5 1826.14  4898.5 1825.86  4906.8 1823.36    4914 1816.92  4915.2 1815.85
  4920.8 1815.31  4929.2 1806.88  4941.2  1806.2  4941.4  1805.7  4945.2  1806.2
    4960 1808.99  4965.5 1807.47  4982.3 1812.68  4987.9 1811.26  5004.7 1813.73
  5010.3 1811.06  5018.6 1815.08  5025.8 1817.03  5032.6 1818.24  5094.1 1820.39
  5116.5 1824.42  5152.8    1845  5161.2 1858.25  5166.8 1864.07  5183.6 1873.95
  5189.1 1875.63  5197.5 1880.49  5211.5 1885.27  5217.1 1888.62  5219.9 1888.62
#Mann= 5 ,-1 , 0
  4884.5    .035       0    4914      .1       0  4941.2     .05       0
  4945.2      .1       0  5025.8      .1       0
#XS Ineff= 2 , 0
                         4982.13         1813.03
Permanent Ineff=
       F       F
Bank Sta=4941.2,4945.2
XS Rating Curve= 0 ,0
Exp/Cntr=0.3,0.1

Type RM Length L Ch R = 1 ,979     ,457,457,457
BEGIN DESCRIPTION:
Stream0207 2.0
END DESCRIPTION:
XS GIS Cut Line= 3
      1852875.01     13935375.01        1852825.       13935325.
      1852674.97     13935174.97
#Sta/Elev= 28
  4924.8 1810.28  4928.4 1810.28    4939 1810.61  4953.1 1809.52  4967.2 1806.85
  4981.4 1799.09    4992 1798.58  4999.1 1798.58  5007.7 1794.72  5007.9 1794.22
  5011.4 1794.22  5011.7 1794.72  5023.8 1796.48    5038 1796.83  5048.6 1797.29
  5052.1 1797.44  5066.2 1797.87  5080.4 1799.15  5094.5  1802.8  5108.7  1808.2
  5122.8 1814.38  5136.9 1821.63  5151.1 1829.45  5165.2 1854.16  5179.4 1862.11
  5193.5 1868.15  5204.1 1871.17  5207.7 1871.17
#Mann= 4 ,-1 , 0
  4924.8      .1       0  5007.7     .05       0  5011.7      .1       0
  5048.6      .1       0
Bank Sta=5007.7,5011.7
XS Rating Curve= 0 ,0
Exp/Cntr=0.3,0.1

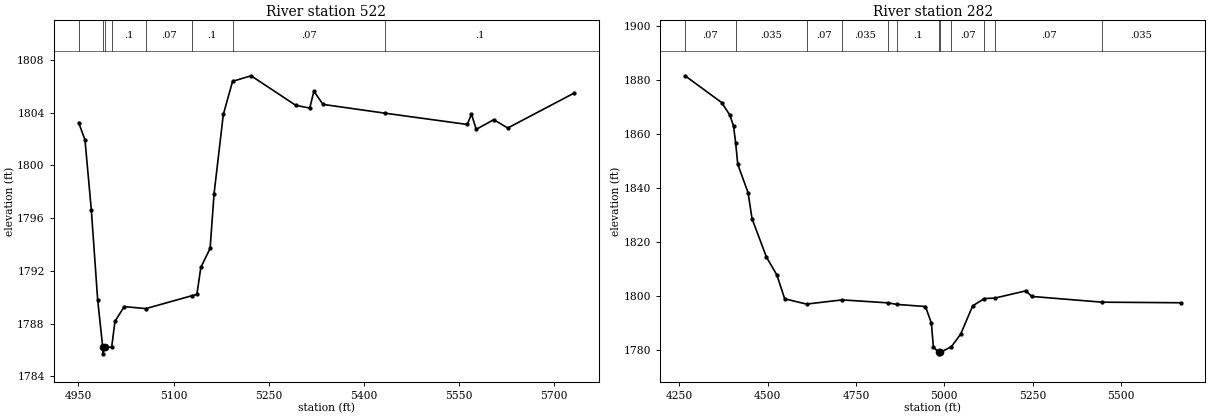
Type RM Length L Ch R = 1 ,522     ,240,240,240
BEGIN DESCRIPTION:
Stream0207 1.0
END DESCRIPTION:
XS GIS Cut Line= 4
        1853225.     13935424.99        1853225.       13935375.
        1853075.       13935175.      1852765.13     13934806.84
#Sta/Elev= 30
  4950.4 1803.24  4960.4 1801.93  4970.4 1796.63  4980.4 1789.81  4988.4 1786.21
  4988.6 1785.71  4992.4 1786.21  5002.5 1786.22  5007.7 1788.18  5022.3 1789.29
  5056.4 1789.14  5128.5 1790.11  5136.8 1790.21  5143.1 1792.27  5157.7 1793.71
  5163.9 1797.85  5178.5 1803.86  5193.1 1806.37  5222.3 1806.79  5292.7 1804.55
  5314.7 1804.34  5321.3 1805.62  5335.6 1804.62    5434 1803.95  5563.1  1803.1
  5569.7 1803.88  5577.2 1802.73  5604.8 1803.46  5626.9 1802.83  5731.6 1805.48
#Mann= 8 ,-1 , 0
  4950.4      .1       0  4988.4     .05       0  4992.4      .1       0
  5002.5      .1       0  5056.4     .07       0  5128.5      .1       0
  5193.1     .07       0    5434      .1       0
Bank Sta=4988.4,4992.4
XS Rating Curve= 0 ,0
Exp/Cntr=0.3,0.1

Type RM Length L Ch R = 1 ,282     ,0,0,0
BEGIN DESCRIPTION:
Stream0207 0.0
END DESCRIPTION:
XS GIS Cut Line= 3
      1853333.05     13936007.48      1853492.21     13935401.39
      1853142.16     13934709.77
#Sta/Elev= 30
  4266.8 1881.42  4370.3  1871.5  4393.4 1866.87  4403.8 1862.81    4410 1856.39
  4415.8 1848.63  4445.1 1838.08  4456.1 1828.52  4496.8 1814.34  4526.5 1807.66
  4548.5 1798.85  4610.3  1796.9  4711.2 1798.45  4840.9 1797.35  4865.2 1796.79
  4946.8 1795.99  4963.5 1789.84  4969.1 1781.08  4983.8 1778.98    4984 1778.48
  4987.8 1778.98    5020  1781.1  5046.3 1785.76  5080.5 1796.28  5113.3 1798.94
  5143.2 1799.12  5230.9 1801.81  5247.5 1799.73  5446.1 1797.61  5668.6 1797.39
#Mann= 12 ,-1 , 0
  4266.8     .07       0    4410    .035       0  4610.3     .07       0
  4711.2    .035       0  4840.9     .07       0  4865.2      .1       0
  4983.8     .05       0  4987.8      .1       0    5020     .07       0
  5113.3      .1       0  5143.2     .07       0  5446.1    .035       0
Bank Sta=4983.8,4987.8
XS Rating Curve= 0 ,0
Exp/Cntr=0.3,0.1

Chan Stop Cuts=-1
Use User Specified Reach Order=0
Composite Channel Slope=5