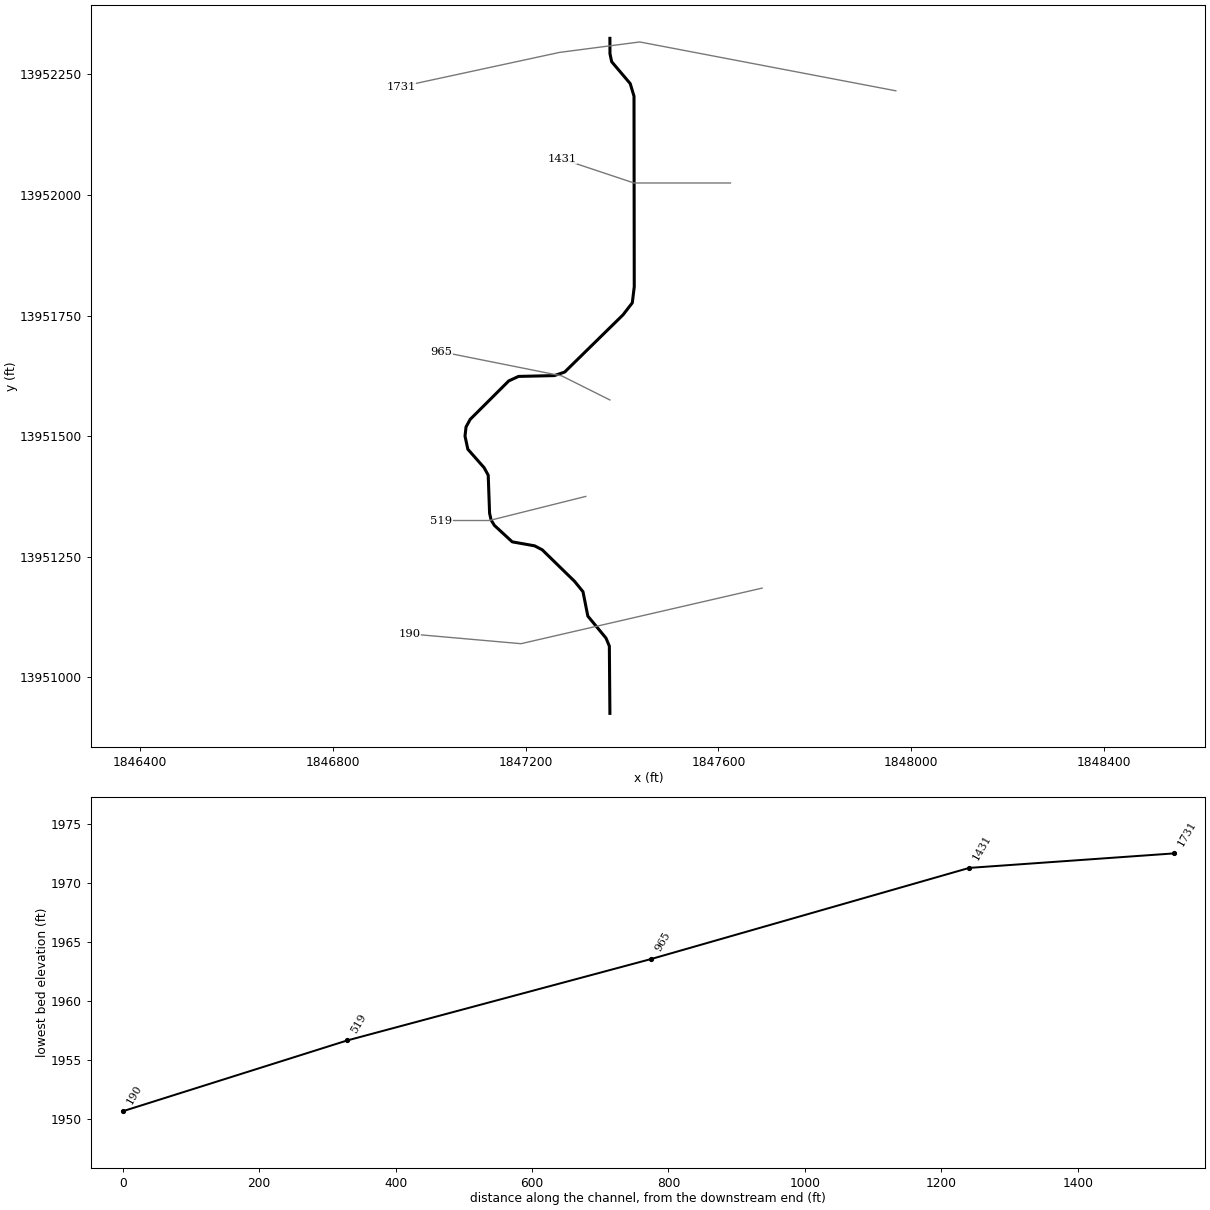
--- Stream0211.prj (project) ---

Proj Title=Stream0211 Base Level Engineering
Current Plan=p01
Default Exp/Contr=0.3,0.1
English Units
Geom File=g01
Flow File=f01
Plan File=p01
BEGIN DESCRIPTION:
Stream0211
END DESCRIPTION:

--- Stream0211.p01 (plan) ---

Plan Title=Multiple Run
Short Identifier=Multiple
Geom File=g01
Flow File=f01
Subcritical Flow
K Sum by GR= 0
Std Step Tol= 0.01
Critical Tol= 0.01
Num of Std Step Trials= 20
Max Error Tol= 0.3
Flow Tol Ratio= 0.001
Split Flow NTrial= 30
Split Flow Tol= 0.02
Split Flow Ratio= 0.02
Log Output Level= 0
Friction Slope Method= 1
Unsteady Friction Slope Method= 2
Unsteady Bridges Friction Slope Method= 1
Parabolic Critical Depth
Global Vel Dist=  1 , 1 , 1
Global Log Level= 0
CheckData=True
Encroach Param= -1, 0, 0, 0
BEGIN DESCRIPTION:
Multiple Run
END DESCRIPTION:

--- Stream0211.f01 (steady flow) ---

Flow Title=Multiple
Number of Profiles=7
Profile Names=10-year,25-year,50-year,1pct_min,100-year,1pct_plu,500-year
River Rch & RM= Stream0211,Reach-1,1731
    1396    2422    3414    2323    4635    9247    8447
River Rch & RM= Stream0211,Reach-1,1431
    1460    2538    3582    2440    4868    9712    8891
Boundary for River Rch & Prof#=Stream0211,Reach-1,1
Up Type=0
Dn Type=3
Dn Slope=0.005
Boundary for River Rch & Prof#=Stream0211,Reach-1,2
Up Type=0
Dn Type=3
Dn Slope=0.005
Boundary for River Rch & Prof#=Stream0211,Reach-1,3
Up Type=0
Dn Type=3
Dn Slope=0.005
Boundary for River Rch & Prof#=Stream0211,Reach-1,4
Up Type=0
Dn Type=3
Dn Slope=0.005
Boundary for River Rch & Prof#=Stream0211,Reach-1,5
Up Type=0
Dn Type=3
Dn Slope=0.005
Boundary for River Rch & Prof#=Stream0211,Reach-1,6
Up Type=0
Dn Type=3
Dn Slope=0.005
Boundary for River Rch & Prof#=Stream0211,Reach-1,7
Up Type=0
Dn Type=3
Dn Slope=0.005

--- Stream0211.g01 (geometry) ---

Geom Title=Existing Conditions

River Reach=Stream0211,Reach-1
Reach XY= 30
      1847375.00     13952325.00      1847375.12     13952293.20
      1847378.65     13952276.51      1847417.11     13952231.16
      1847424.98     13952204.99      1847425.49     13951809.80
      1847421.46     13951776.46      1847402.14     13951751.47
      1847281.17     13951632.86      1847259.78     13951625.53
      1847185.48     13951623.84      1847165.19     13951614.49
      1847085.18     13951534.71      1847076.61     13951518.98
      1847074.50     13951500.04      1847080.35     13951472.83
      1847114.04     13951434.65      1847122.61     13951419.03
      1847125.47     13951340.09      1847128.52     13951326.28
      1847135.39     13951314.90      1847172.43     13951280.74
      1847218.92     13951272.45      1847234.68     13951264.22
      1847302.01     13951198.52      1847319.18     13951177.31
      1847329.22     13951126.75      1847366.92     13951081.08
      1847373.85     13951064.52      1847375.00     13950925.00

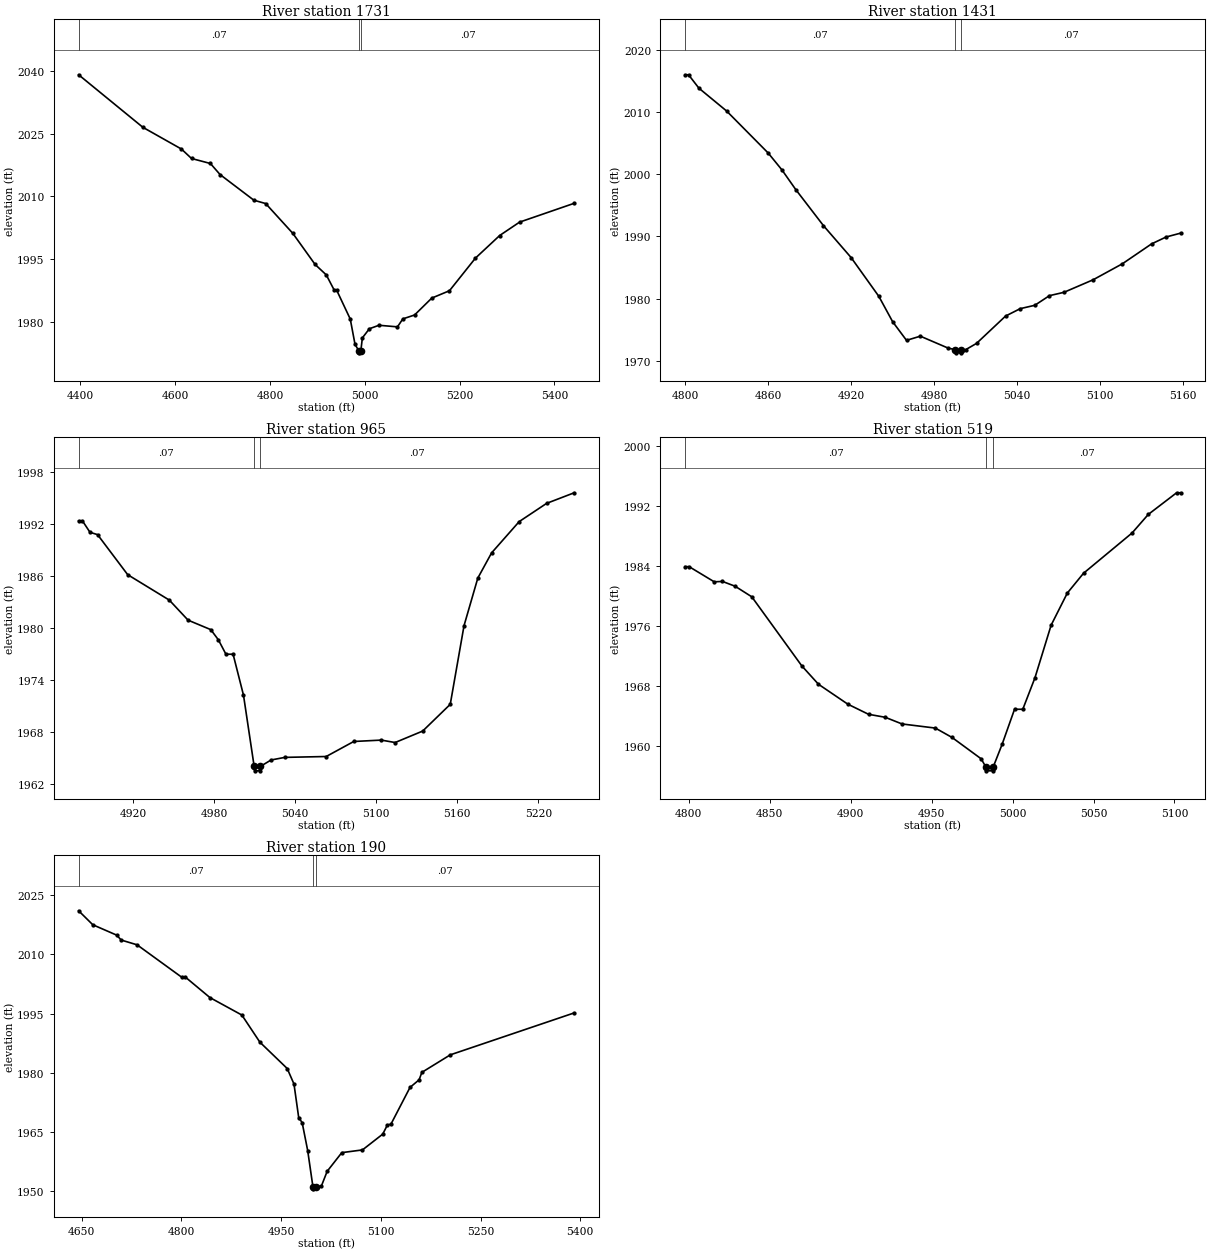
Type RM Length L Ch R = 1,1731,300,300,300
BEGIN DESCRIPTION:
Stream0211 4.0
END DESCRIPTION:
XS GIS Cut Line= 4
      1847968.01     13952216.18      1847436.89     13952317.50
      1847270.54     13952295.83      1846941.47     13952224.79
#Sta/Elev= 30
  4396.5 2039.08  4531.9 2026.51  4613.3 2021.30  4634.6 2019.04  4674.4 2017.84
  4694.8 2015.19  4766.1 2009.05  4791.0 2008.25  4848.2 2001.12  4895.2 1993.67
  4918.8 1991.17  4935.6 1987.51  4940.7 1987.51  4969.4 1980.59  4979.4 1974.55
  4987.3 1973.01  4987.6 1972.51  4991.7 1973.01  4994.9 1976.09  5009.7 1978.28
  5029.9 1979.11  5068.9 1978.73  5080.3 1980.64  5105.0 1981.57  5141.3 1985.62
  5178.6 1987.38  5233.4 1995.19  5284.5 2000.60  5326.4 2003.80  5441.6 2008.31
#Mann=3,-1,0
  4396.5    0.07       0  4987.3    0.05       0  4991.7    0.07       0
Bank Sta=4987.3,4991.7
Exp/Cntr=0.3,0.1

Type RM Length L Ch R = 1,1431,466,466,466
BEGIN DESCRIPTION:
Stream0211 3.0
END DESCRIPTION:
XS GIS Cut Line= 3
      1847625.02     13952025.00      1847425.00     13952025.00
      1847275.03     13952074.99
#Sta/Elev= 30
  4800.0 2016.02  4802.5 2016.02  4810.0 2013.86  4830.0 2010.19  4860.0 2003.44
  4870.0 2000.71  4880.0 1997.54  4900.0 1991.74  4920.0 1986.60  4940.0 1980.37
  4950.0 1976.28  4960.0 1973.29  4970.0 1973.96  4990.0 1972.05  4995.3 1971.78
  4995.6 1971.28  4999.4 1971.28  4999.7 1971.78  5002.7 1971.78  5010.6 1972.80
  5031.6 1977.20  5042.2 1978.39  5052.7 1978.93  5063.3 1980.48  5073.8 1981.02
  5094.9 1983.04  5116.0 1985.61  5137.1 1988.81  5147.6 1989.92  5158.1 1990.54
#Mann=3,-1,0
  4800.0    0.07       0  4995.3    0.05       0  4999.7    0.07       0
Bank Sta=4995.3,4999.7
Exp/Cntr=0.3,0.1

Type RM Length L Ch R = 1,965,446,446,446
BEGIN DESCRIPTION:
Stream0211 2.0
END DESCRIPTION:
XS GIS Cut Line= 3
      1847374.99     13951575.00      1847275.00     13951625.00
      1847025.05     13951674.99
#Sta/Elev= 30
  4879.8 1992.34  4882.6 1992.34  4888.2 1991.02  4893.8 1990.75  4916.1 1986.14
  4946.9 1983.21  4960.8 1980.90  4977.6 1979.81  4983.2 1978.64  4988.8 1976.98
  4994.1 1976.98  5001.8 1972.26  5009.7 1964.05  5010.0 1963.55  5013.9 1963.55
  5014.2 1964.05  5022.2 1964.80  5032.4 1965.10  5063.0 1965.20  5083.4 1966.93
  5103.8 1967.09  5114.0 1966.81  5134.4 1968.13  5154.8 1971.21  5165.0 1980.27
  5175.2 1985.75  5185.4 1988.65  5205.8 1992.25  5226.1 1994.35  5246.5 1995.57
#Mann=3,-1,0
  4879.8    0.07       0  5009.7    0.05       0  5014.2    0.07       0
Bank Sta=5009.7,5014.2
Exp/Cntr=0.3,0.1

Type RM Length L Ch R = 1,519,329,329,329
BEGIN DESCRIPTION:
Stream0211 1.0
END DESCRIPTION:
XS GIS Cut Line= 3
      1847324.95     13951374.99      1847125.00     13951325.00
      1847025.01     13951325.00
#Sta/Elev= 30
  4797.7 1983.85  4800.2 1983.85  4815.7 1981.83  4820.8 1981.88  4828.6 1981.24
  4838.9 1979.83  4869.8 1970.62  4880.1 1968.17  4898.2 1965.52  4911.0 1964.17
  4921.3 1963.77  4931.7 1962.88  4952.3 1962.33  4962.6 1961.08  4980.6 1958.23
  4983.5 1957.13  4983.8 1956.63  4987.7 1956.63  4988.0 1957.13  4993.5 1960.15
  5001.2 1964.84  5006.3 1964.84  5013.8 1969.03  5023.8 1976.05  5033.8 1980.33
  5043.8 1982.97  5073.8 1988.34  5083.8 1990.81  5101.3 1993.70  5103.8 1993.70
#Mann=3,-1,0
  4797.7    0.07       0  4983.5    0.05       0  4988.0    0.07       0
Bank Sta=4983.5,4988
Exp/Cntr=0.3,0.1

Type RM Length L Ch R = 1,190,0,0,0
BEGIN DESCRIPTION:
Stream0211 0.0
END DESCRIPTION:
XS GIS Cut Line= 3
      1847690.67     13951184.79      1847190.61     13951069.52
      1846959.38     13951089.94
#Sta/Elev= 30
  4645.5 2021.05  4666.8 2017.51  4702.6 2014.89  4709.6 2013.63  4733.4 2012.43
  4800.3 2004.25  4805.4 2004.34  4843.0 1999.06  4891.0 1994.64  4918.1 1987.77
  4959.2 1981.10  4969.4 1977.16  4976.5 1968.65  4981.7 1967.39  4990.0 1960.32
  4997.9 1951.12  4998.3 1950.62  5002.5 1951.12  5010.5 1951.28  5019.3 1955.06
  5041.3 1959.79  5072.4 1960.48  5102.9 1964.48  5110.0 1966.83  5115.1 1966.96
  5143.9 1976.31  5157.6 1978.24  5161.7 1980.12  5204.5 1984.56  5390.8 1995.18
#Mann=3,-1,0
  4645.5    0.07       0  4997.9    0.05       0  5002.5    0.07       0
Bank Sta=4997.9,5002.5
Exp/Cntr=0.3,0.1

Chan Stop Cuts=-1