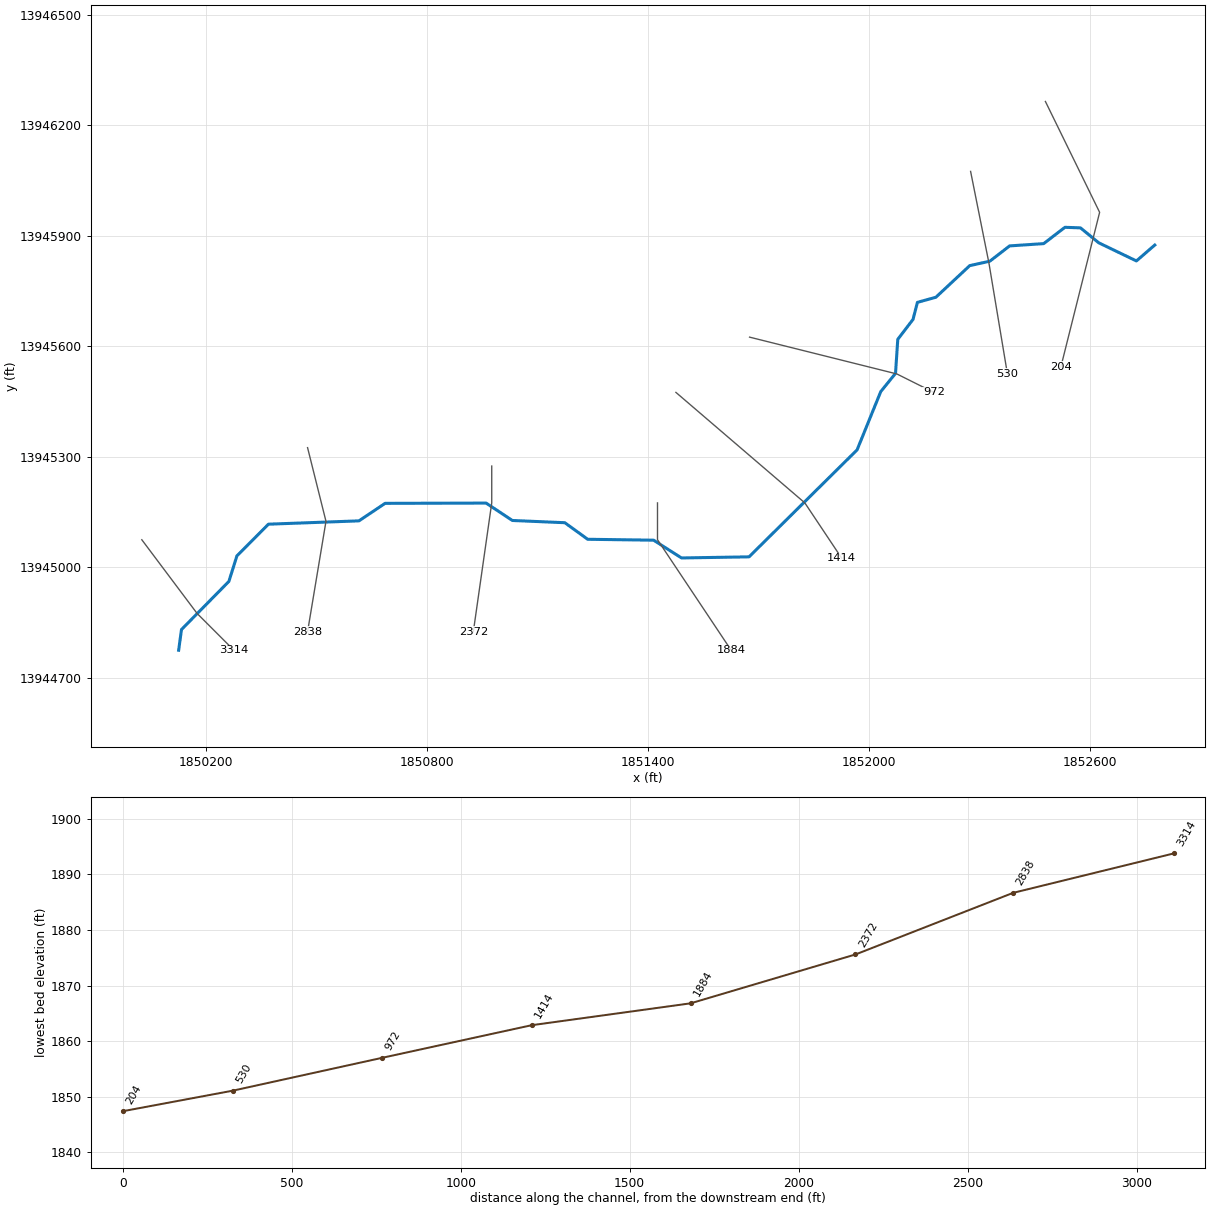
--- Stream0212.prj (project) ---

Proj Title=Stream0212 Base Level Engineering
Current Plan=p01
Default Exp/Contr=0.3,0.1
English Units
Geom File=g01
Flow File=f01
Plan File=p01
BEGIN DESCRIPTION:
Stream0212
END DESCRIPTION:

--- Stream0212.p01 (plan) ---

Plan Title=Multiple Run
Short Identifier=Multiple
Geom File=g01
Flow File=f01
Subcritical Flow
K Sum by GR= 0
Std Step Tol= 0.01
Critical Tol= 0.01
Num of Std Step Trials= 20
Max Error Tol= 0.3
Flow Tol Ratio= 0.001
Split Flow NTrial= 30
Split Flow Tol= 0.02
Split Flow Ratio= 0.02
Log Output Level= 0
Friction Slope Method= 1
Unsteady Friction Slope Method= 2
Unsteady Bridges Friction Slope Method= 1
Parabolic Critical Depth
Global Vel Dist=  1 , 1 , 1
Global Log Level= 0
CheckData=True
Encroach Param= -1, 0, 0, 0
BEGIN DESCRIPTION:
Multiple Run
END DESCRIPTION:

--- Stream0212.f01 (steady flow) ---

Flow Title=Multiple
Number of Profiles=7
Profile Names=10-year,25-year,50-year,1pct_min,100-year,1pct_plu,500-year
River Rch & RM= Stream0212,Reach-1,3314
    1990    3546    5089    3524    7032   14030   13279
Boundary for River Rch & Prof#=Stream0212,Reach-1,1
Up Type=0
Dn Type=3
Dn Slope=0.005
Boundary for River Rch & Prof#=Stream0212,Reach-1,2
Up Type=0
Dn Type=3
Dn Slope=0.005
Boundary for River Rch & Prof#=Stream0212,Reach-1,3
Up Type=0
Dn Type=3
Dn Slope=0.005
Boundary for River Rch & Prof#=Stream0212,Reach-1,4
Up Type=0
Dn Type=3
Dn Slope=0.005
Boundary for River Rch & Prof#=Stream0212,Reach-1,5
Up Type=0
Dn Type=3
Dn Slope=0.005
Boundary for River Rch & Prof#=Stream0212,Reach-1,6
Up Type=0
Dn Type=3
Dn Slope=0.005
Boundary for River Rch & Prof#=Stream0212,Reach-1,7
Up Type=0
Dn Type=3
Dn Slope=0.005

--- Stream0212.g01 (geometry) ---

Geom Title=Existing Conditions

River Reach=Stream0212,Reach-1
Reach XY= 30
      1850125.00     13944775.00      1850132.76     13944831.21
      1850261.37     13944961.79      1850283.15     13945031.07
      1850368.79     13945117.20      1850614.50     13945126.22
      1850685.50     13945173.78      1850959.78     13945174.48
      1851030.94     13945127.27      1851173.43     13945121.21
      1851235.51     13945076.22      1851414.49     13945073.78
      1851490.22     13945025.52      1851673.54     13945028.53
      1851966.86     13945318.94      1852031.12     13945477.18
      1852071.17     13945526.59      1852077.32     13945619.06
      1852118.72     13945673.16      1852130.59     13945719.39
      1852180.74     13945733.30      1852272.71     13945819.16
      1852327.17     13945831.14      1852380.97     13945872.67
      1852473.42     13945878.89      1852531.12     13945923.18
      1852573.28     13945921.66      1852622.81     13945881.13
      1852725.12     13945831.87      1852775.00     13945875.00

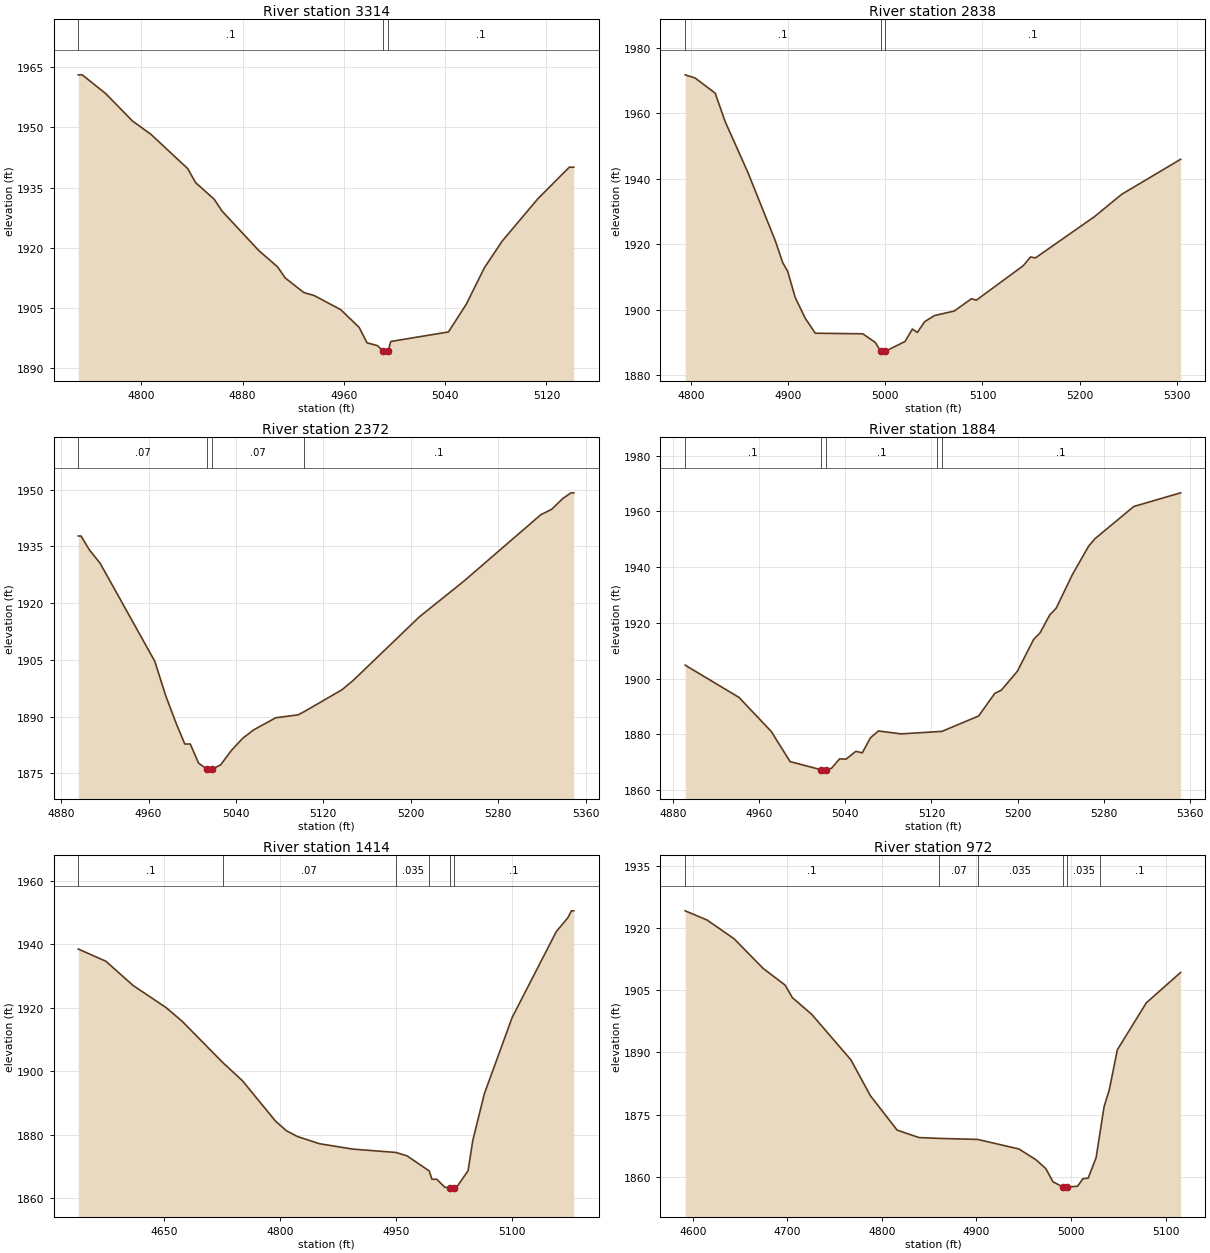
Type RM Length L Ch R = 1,3314,476,476,476
BEGIN DESCRIPTION:
Stream0212 7.0
END DESCRIPTION:
XS GIS Cut Line= 3
      1850025.02     13945074.97      1850175.00     13944875.00
      1850275.01     13944774.99
#Sta/Elev= 30
  4750.2 1963.11  4753.3 1963.11  4772.0 1958.39  4792.9 1951.63  4807.5 1948.30
  4836.6 1939.75  4842.9 1936.23  4857.5 1932.13  4863.7 1929.18  4892.9 1919.28
  4907.5 1915.30  4913.7 1912.48  4928.3 1908.87  4936.6 1908.10  4957.5 1904.59
  4972.0 1900.20  4978.3 1896.33  4986.6 1895.62  4990.8 1894.26  4991.1 1893.76
  4994.7 1893.76  4995.0 1894.26  4997.0 1896.66  5042.6 1899.04  5056.7 1905.95
  5070.9 1914.98  5085.0 1921.66  5113.3 1932.25  5138.1 1940.09  5141.6 1940.09
#Mann=3,-1,0
  4750.2     0.1       0  4990.8    0.05       0  4995.0     0.1       0
Bank Sta=4990.8,4995
Exp/Cntr=0.3,0.1

Type RM Length L Ch R = 1,2838,466,466,466
BEGIN DESCRIPTION:
Stream0212 6.0
END DESCRIPTION:
XS GIS Cut Line= 3
      1850475.01     13945324.97      1850525.00     13945125.00
      1850474.99     13944824.97
#Sta/Elev= 30
  4793.8 1971.76  4804.1 1970.78  4824.7 1966.15  4835.0 1957.43  4858.2 1942.05
  4886.5 1921.10  4894.3 1914.31  4899.4 1911.63  4907.2 1903.62  4917.5 1897.30
  4927.8 1892.75  4976.7 1892.57  4989.6 1889.94  4995.3 1887.16  4995.5 1886.66
  4999.5 1887.16  5020.2 1890.22  5027.8 1894.02  5032.9 1892.99  5040.5 1896.29
  5050.6 1898.15  5070.9 1899.53  5088.6 1903.29  5093.7 1902.86  5141.9 1913.37
  5149.5 1916.06  5154.5 1915.77  5215.4 1928.40  5243.2 1935.19  5304.1 1945.94
#Mann=3,-1,0
  4793.8     0.1       0  4995.3    0.05       0  4999.5     0.1       0
Bank Sta=4995.3,4999.5
Exp/Cntr=0.3,0.1

Type RM Length L Ch R = 1,2372,488,488,488
BEGIN DESCRIPTION:
Stream0212 5.0
END DESCRIPTION:
XS GIS Cut Line= 3
      1850975.00     13945274.99      1850975.00     13945175.00
      1850925.01     13944825.05
#Sta/Elev= 30
  4895.7 1937.77  4898.2 1937.77  4905.7 1934.17  4915.7 1930.55  4965.7 1904.64
  4975.7 1895.55  4985.7 1887.91  4993.2 1882.76  4998.2 1882.76  5005.8 1877.70
  5013.7 1876.09  5014.0 1875.59  5017.8 1875.59  5018.1 1876.09  5026.0 1877.26
  5036.1 1881.16  5046.2 1884.28  5056.3 1886.52  5076.5 1889.71  5096.7 1890.46
  5102.7 1891.36  5137.1 1897.12  5147.2 1899.55  5207.8 1916.37  5248.2 1925.73
  5318.9 1943.37  5329.0 1944.84  5339.1 1947.67  5346.7 1949.19  5349.2 1949.19
#Mann=4,-1,0
  4895.7    0.07       0  5013.7    0.05       0  5018.1    0.07       0
  5102.7     0.1       0
Bank Sta=5013.7,5018.1
Exp/Cntr=0.3,0.1

Type RM Length L Ch R = 1,1884,470,470,470
BEGIN DESCRIPTION:
Stream0212 4.0
END DESCRIPTION:
XS GIS Cut Line= 3
      1851425.00     13945174.96      1851425.00     13945075.00
      1851624.99     13944775.02
#Sta/Elev= 30
  4891.1 1904.81  4941.1 1893.25  4971.1 1881.03  4988.6 1870.22  5017.4 1867.30
  5017.7 1866.80  5021.9 1867.30  5027.1 1867.83  5034.6 1871.20  5040.6 1871.10
  5049.7 1873.90  5055.7 1873.36  5063.2 1878.72  5070.7 1881.21  5091.7 1880.16
  5124.9 1880.95  5129.6 1881.04  5163.8 1886.57  5178.9 1894.71  5184.9 1895.82
  5199.9 1902.66  5214.9 1914.02  5220.9 1916.39  5229.9 1922.80  5235.9 1925.24
  5251.0 1937.31  5266.0 1947.45  5272.0 1950.18  5308.1 1961.74  5351.6 1966.63
#Mann=5,-1,0
  4891.1     0.1       0  5017.4    0.05       0  5021.9     0.1       0
  5124.9   0.035       0  5129.6     0.1       0
Bank Sta=5017.4,5021.9
Exp/Cntr=0.3,0.1

Type RM Length L Ch R = 1,1414,442,442,442
BEGIN DESCRIPTION:
Stream0212 3.0
END DESCRIPTION:
XS GIS Cut Line= 3
      1851475.00     13945475.00      1851825.00     13945175.00
      1851925.02     13945024.97
#Sta/Elev= 30
  4539.0 1938.49  4574.7 1934.65  4609.8 1927.04  4652.6 1920.05  4673.5 1915.72
  4725.8 1902.78  4751.4 1897.03  4794.2 1884.32  4808.5 1881.24  4822.7 1879.43
  4851.3 1877.17  4894.1 1875.48  4950.1 1874.42  4964.3 1873.38  4993.3 1868.58
  4996.7 1865.98  5003.0 1865.98  5013.5 1863.44  5020.3 1863.37  5020.6 1862.87
  5024.8 1863.37  5028.5 1863.39  5043.5 1868.68  5049.6 1878.19  5064.6 1892.94
  5100.6 1916.96  5157.7 1943.99  5172.7 1948.36  5177.3 1950.53  5180.3 1950.53
#Mann=6,-1,0
  4539.0     0.1       0  4725.8    0.07       0  4950.1   0.035       0
  4993.3     0.1       0  5020.3    0.05       0  5024.8     0.1       0
Bank Sta=5020.3,5024.8
Exp/Cntr=0.3,0.1

Type RM Length L Ch R = 1,972,442,442,442
BEGIN DESCRIPTION:
Stream0212 2.0
END DESCRIPTION:
XS GIS Cut Line= 3
      1851674.98     13945625.00      1852075.00     13945525.00
      1852174.97     13945475.02
#Sta/Elev= 30
  4591.9 1924.15  4615.1 1921.93  4643.5 1917.43  4674.4 1910.25  4697.6 1906.23
  4705.3 1903.20  4725.9 1899.14  4767.2 1888.20  4787.8 1879.55  4816.1 1871.24
  4839.3 1869.45  4860.5 1869.25  4901.3 1869.00  4945.0 1866.69  4963.0 1864.09
  4973.3 1861.98  4981.0 1858.78  4991.6 1857.51  4992.0 1857.01  4996.2 1857.51
  5007.0 1857.71  5012.6 1859.53  5018.2 1859.66  5026.6 1864.62  5030.2 1869.87
  5035.0 1876.88  5040.6 1881.04  5049.0 1890.61  5079.7 1901.96  5116.0 1909.29
#Mann=6,-1,0
  4591.9     0.1       0  4860.5    0.07       0  4901.3   0.035       0
  4991.6   0.035       0  4996.2   0.035       0  5030.2     0.1       0
Bank Sta=4991.6,4996.2
Exp/Cntr=0.3,0.1

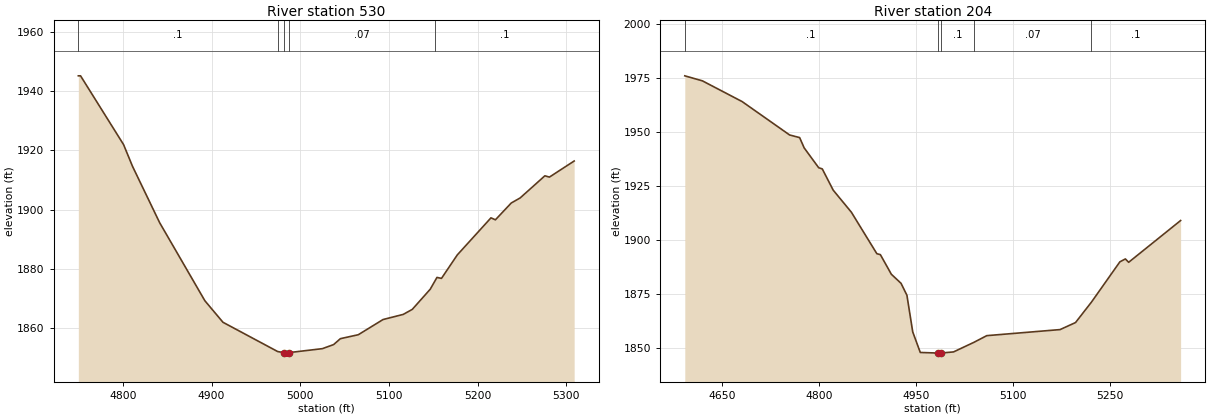
Type RM Length L Ch R = 1,530,326,326,326
BEGIN DESCRIPTION:
Stream0212 1.0
END DESCRIPTION:
XS GIS Cut Line= 3
      1852275.01     13946074.96      1852325.00     13945825.00
      1852375.01     13945524.95
#Sta/Elev= 30
  4749.8 1945.22  4752.3 1945.22  4800.8 1921.97  4810.9 1914.61  4841.5 1895.55
  4892.5 1869.15  4912.9 1861.87  4974.6 1851.97  4981.7 1851.60  4982.1 1851.10
  4986.9 1851.60  5025.0 1852.95  5037.7 1854.33  5045.3 1856.33  5065.5 1857.66
  5093.4 1862.80  5116.2 1864.54  5126.4 1866.24  5146.6 1873.05  5151.5 1875.62
  5154.2 1877.04  5159.3 1876.72  5177.1 1884.64  5215.1 1897.19  5220.1 1896.52
  5237.9 1902.19  5248.0 1903.92  5275.9 1911.41  5281.0 1910.97  5308.9 1916.41
#Mann=5,-1,0
  4749.8     0.1       0  4974.6    0.07       0  4981.7    0.05       0
  4986.9    0.07       0  5151.5     0.1       0
Bank Sta=4981.7,4986.9
Exp/Cntr=0.3,0.1

Type RM Length L Ch R = 1,204,0,0,0
BEGIN DESCRIPTION:
Stream0212 0.0
END DESCRIPTION:
XS GIS Cut Line= 3
      1852478.12     13946264.79      1852625.31     13945963.85
      1852519.97     13945543.76
#Sta/Elev= 30
  4592.0 1975.90  4619.3 1973.58  4680.8 1964.01  4754.4 1948.59  4769.9 1947.38
  4776.9 1942.64  4799.4 1933.47  4805.0 1932.91  4821.9 1923.11  4850.0 1912.95
  4889.5 1893.78  4895.0 1893.33  4912.0 1884.27  4927.0 1880.09  4936.1 1874.59
  4945.1 1857.67  4956.8 1848.17  4983.6 1847.90  4984.0 1847.40  4988.8 1847.90
  5008.3 1848.42  5039.7 1852.82  5059.8 1855.93  5173.3 1858.73  5197.3 1861.98
  5222.0 1871.43  5266.0 1890.02  5274.5 1891.35  5279.6 1889.80  5360.1 1909.09
#Mann=5,-1,0
  4592.0     0.1       0  4983.6    0.05       0  4988.8     0.1       0
  5039.7    0.07       0  5222.0     0.1       0
Bank Sta=4983.6,4988.8
Exp/Cntr=0.3,0.1

Chan Stop Cuts=-1