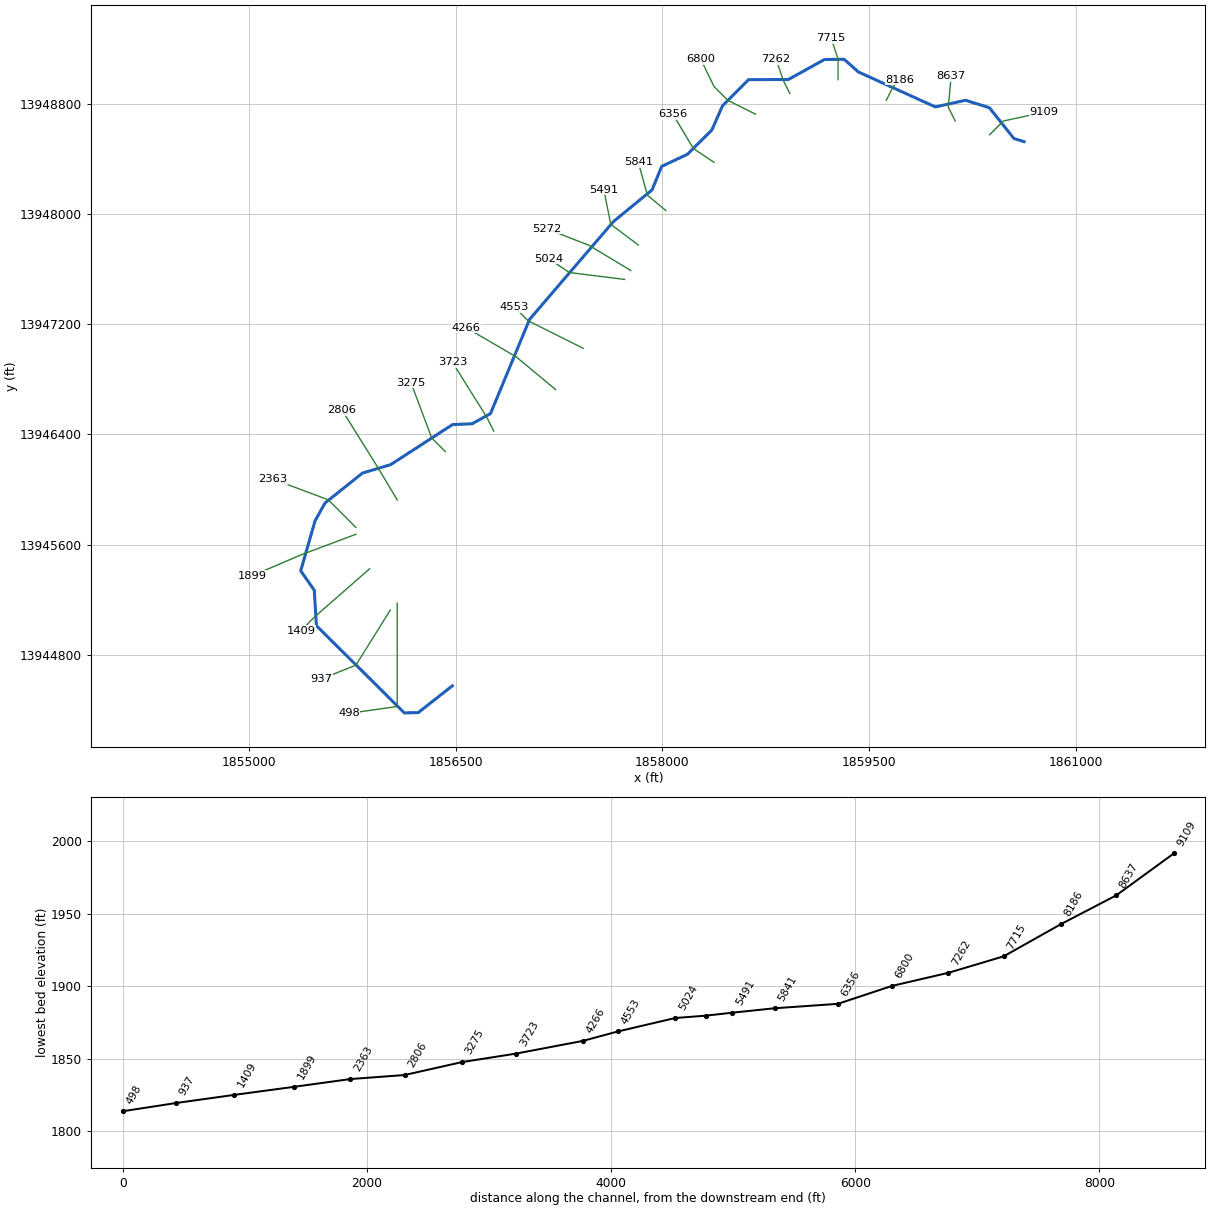
--- Stream0213.prj (project) ---

Proj Title=Stream0213 Base Level Engineering
Current Plan=p01
Default Exp/Contr=0.3,0.1
English Units
Geom File=g01
Flow File=f01
Plan File=p01
BEGIN DESCRIPTION:
Stream0213
END DESCRIPTION:

--- Stream0213.p01 (plan) ---

Plan Title=Multiple Run
Short Identifier=Multiple
Geom File=g01
Flow File=f01
Subcritical Flow
K Sum by GR= 0
Std Step Tol= 0.01
Critical Tol= 0.01
Num of Std Step Trials= 20
Max Error Tol= 0.3
Flow Tol Ratio= 0.001
Split Flow NTrial= 30
Split Flow Tol= 0.02
Split Flow Ratio= 0.02
Log Output Level= 0
Friction Slope Method= 1
Unsteady Friction Slope Method= 2
Unsteady Bridges Friction Slope Method= 1
Parabolic Critical Depth
Global Vel Dist=  1 , 1 , 1
Global Log Level= 0
CheckData=True
Encroach Param= -1, 0, 0, 0
BEGIN DESCRIPTION:
Multiple Run
END DESCRIPTION:

--- Stream0213.f01 (steady flow) ---

Flow Title=Multiple
Number of Profiles=7
Profile Names=10-year,25-year,50-year,1pct_min,100-year,1pct_plu,500-year
River Rch & RM= Stream0213,Reach-1,9109
     721    1207    1661    1109    2213    4416    3872
River Rch & RM= Stream0213,Reach-1,6800
    1153    1985    2784    1889    3769    7519    6821
River Rch & RM= Stream0213,Reach-1,5841
    1393    2424    3425    2338    4666    9310    8556
River Rch & RM= Stream0213,Reach-1,5272
    2252    4023    5782    4010    8001   15964   15148
Boundary for River Rch & Prof#=Stream0213,Reach-1,1
Up Type=0
Dn Type=3
Dn Slope=0.005
Boundary for River Rch & Prof#=Stream0213,Reach-1,2
Up Type=0
Dn Type=3
Dn Slope=0.005
Boundary for River Rch & Prof#=Stream0213,Reach-1,3
Up Type=0
Dn Type=3
Dn Slope=0.005
Boundary for River Rch & Prof#=Stream0213,Reach-1,4
Up Type=0
Dn Type=3
Dn Slope=0.005
Boundary for River Rch & Prof#=Stream0213,Reach-1,5
Up Type=0
Dn Type=3
Dn Slope=0.005
Boundary for River Rch & Prof#=Stream0213,Reach-1,6
Up Type=0
Dn Type=3
Dn Slope=0.005
Boundary for River Rch & Prof#=Stream0213,Reach-1,7
Up Type=0
Dn Type=3
Dn Slope=0.005

--- Stream0213.g01 (geometry) ---

Geom Title=Existing Conditions

River Reach=Stream0213,Reach-1
Reach XY= 30
      1860625.00     13948525.00      1860551.48     13948548.02
      1860373.52     13948771.39      1860200.00     13948825.40
      1859980.94     13948777.25      1859422.71     13949030.85
      1859319.14     13949122.95      1859176.47     13949121.46
      1858914.50     13948976.22      1858625.00     13948975.00
      1858435.76     13948784.68      1858358.36     13948608.32
      1858181.06     13948433.14      1857994.62     13948345.48
      1857925.00     13948175.00      1857644.77     13947945.13
      1857035.52     13947234.79      1856752.15     13946551.16
      1856619.07     13946477.25      1856476.56     13946471.24
      1856027.42     13946180.54      1855822.70     13946119.17
      1855551.16     13945902.14      1855478.82     13945773.42
      1855374.47     13945409.81      1855472.93     13945269.14
      1855488.37     13945011.68      1856126.50     13944378.46
      1856227.43     13944380.40      1856475.00     13944575.00

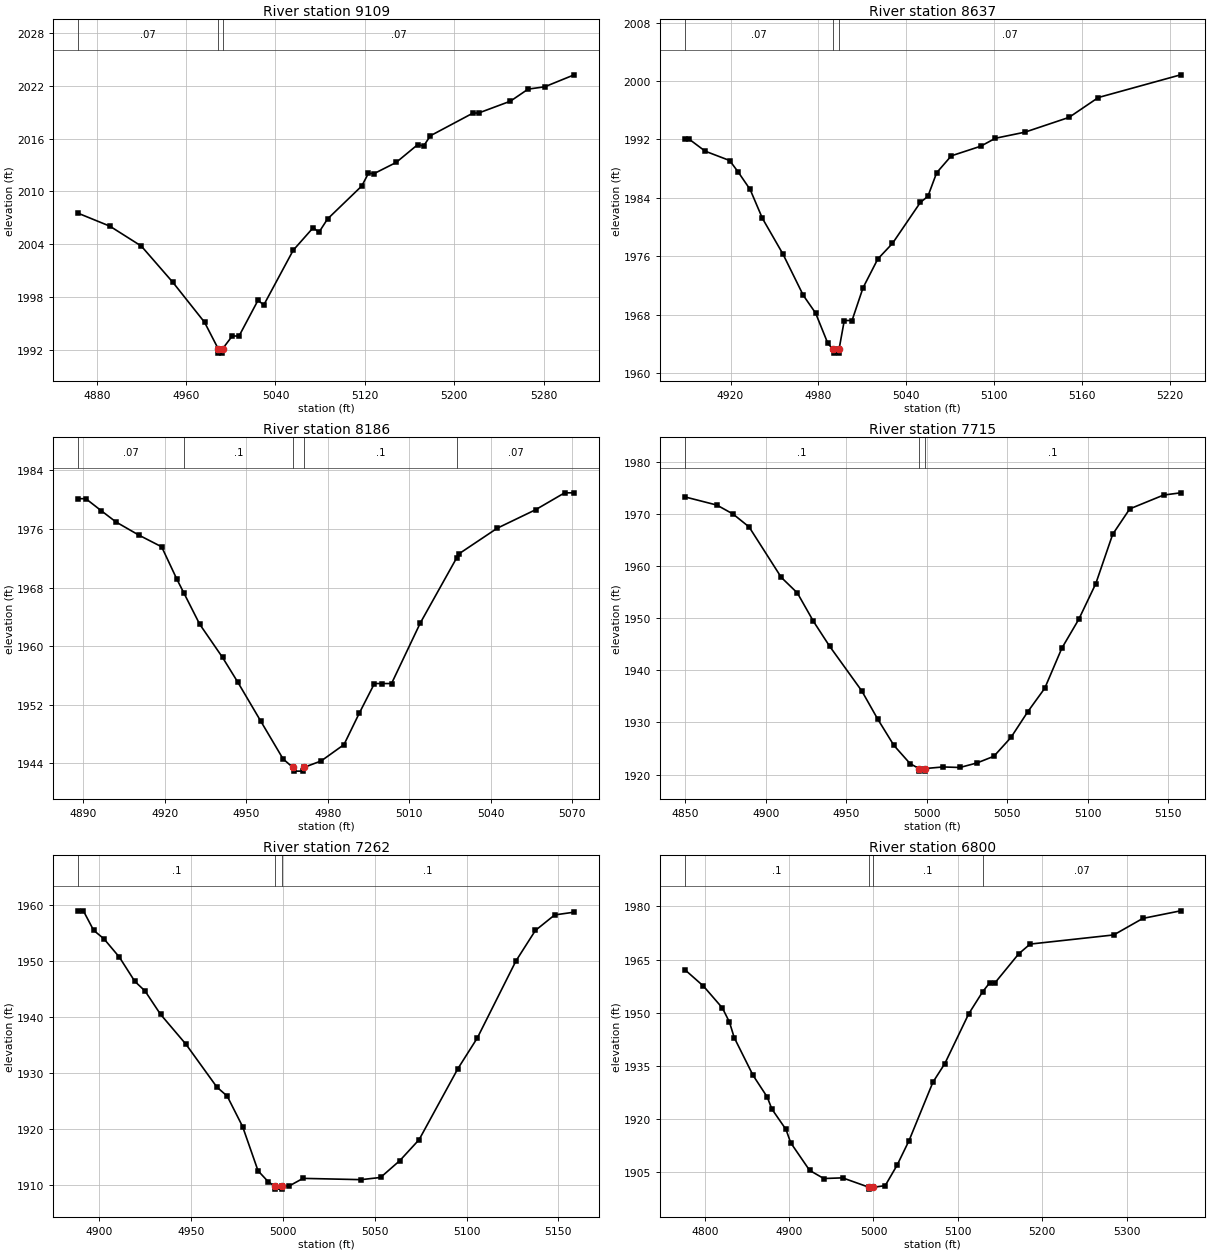
Type RM Length L Ch R = 1,9109,472,472,472
BEGIN DESCRIPTION:
Stream0213 20.0
END DESCRIPTION:
XS GIS Cut Line= 3
      1860375.01     13948575.01      1860475.00     13948675.00
      1860770.86     13948738.52
#Sta/Elev= 30
  4863.4 2007.53  4891.7 2006.07  4919.9 2003.81  4948.2 1999.69  4976.5 1995.17
  4988.7 1992.17  4988.9 1991.67  4992.4 1991.67  4992.7 1992.17  5001.3 1993.61
  5007.4 1993.61  5024.4 1997.67  5029.5 1997.12  5055.9 2003.34  5073.8 2005.90
  5078.9 2005.37  5086.6 2006.88  5117.3 2010.63  5123.2 2012.06  5128.3 2012.03
  5148.0 2013.29  5167.4 2015.32  5172.6 2015.15  5178.7 2016.32  5216.8 2018.89
  5221.9 2018.90  5250.3 2020.24  5266.2 2021.61  5281.0 2021.87  5307.4 2023.23
#Mann=3,-1,0
  4863.4    0.07       0  4988.7    0.05       0  4992.7    0.07       0
Bank Sta=4988.7,4992.7
Exp/Cntr=0.3,0.1

Type RM Length L Ch R = 1,8637,451,451,451
BEGIN DESCRIPTION:
Stream0213 19.0
END DESCRIPTION:
XS GIS Cut Line= 3
      1860125.00     13948675.01      1860075.00     13948775.00
      1860096.28     13949000.91
#Sta/Elev= 30
  4888.7 1992.08  4891.5 1992.08  4902.7 1990.40  4919.4 1989.12  4925.0 1987.61
  4933.4 1985.15  4941.8 1981.19  4955.8 1976.31  4969.7 1970.65  4978.1 1968.22
  4986.5 1964.05  4990.1 1963.23  4990.4 1962.73  4993.9 1962.73  4994.1 1963.23
  4997.7 1967.20  5003.0 1967.20  5010.5 1971.68  5020.6 1975.63  5030.6 1977.76
  5049.7 1983.39  5054.8 1984.21  5060.8 1987.45  5070.8 1989.76  5090.9 1991.08
  5100.9 1992.17  5121.0 1993.00  5151.2 1995.03  5171.2 1997.75  5227.4 2000.86
#Mann=3,-1,0
  4888.7    0.07       0  4990.1    0.05       0  4994.1    0.07       0
Bank Sta=4990.1,4994.1
Exp/Cntr=0.3,0.1

Type RM Length L Ch R = 1,8186,471,471,471
BEGIN DESCRIPTION:
Stream0213 18.0
END DESCRIPTION:
XS GIS Cut Line= 3
      1859625.01     13948825.02      1859675.00     13948925.00
      1859725.01     13948975.01
#Sta/Elev= 30
  4888.2 1980.15  4891.0 1980.15  4896.6 1978.53  4902.1 1976.97  4910.5 1975.18
  4918.9 1973.58  4924.5 1969.16  4927.1 1967.26  4932.9 1963.01  4941.3 1958.48
  4946.9 1955.11  4955.3 1949.82  4963.6 1944.61  4967.2 1943.45  4967.5 1942.95
  4971.0 1942.95  4971.2 1943.45  4977.6 1944.34  4986.0 1946.57  4991.6 1950.84
  4997.2 1954.91  5000.0 1954.91  5003.5 1954.91  5014.1 1963.19  5027.5 1972.09
  5028.3 1972.62  5042.4 1976.12  5056.5 1978.64  5067.2 1980.95  5070.7 1980.95
#Mann=5,-1,0
  4888.2    0.07       0  4927.1     0.1       0  4967.2    0.05       0
  4971.2     0.1       0  5027.5    0.07       0
Bank Sta=4967.2,4971.2
Exp/Cntr=0.3,0.1

Type RM Length L Ch R = 1,7715,453,453,453
BEGIN DESCRIPTION:
Stream0213 17.0
END DESCRIPTION:
XS GIS Cut Line= 3
      1859275.00     13948975.04      1859275.00     13949125.00
      1859224.99     13949275.02
#Sta/Elev= 30
  4849.5 1973.27  4869.5 1971.69  4879.5 1969.98  4889.5 1967.50  4909.5 1957.82
  4919.5 1954.83  4929.5 1949.38  4939.5 1944.63  4959.5 1936.05  4969.5 1930.59
  4979.5 1925.58  4989.5 1922.10  4995.0 1921.15  4995.2 1920.65  4998.7 1920.65
  4999.0 1921.15  5010.0 1921.45  5020.5 1921.35  5031.1 1922.22  5041.6 1923.50
  5052.2 1927.11  5062.7 1932.07  5073.2 1936.55  5083.8 1944.23  5094.3 1949.76
  5104.9 1956.62  5115.4 1966.09  5126.0 1970.96  5147.0 1973.61  5157.6 1974.04
#Mann=3,-1,0
  4849.5     0.1       0  4995.0    0.05       0  4999.0     0.1       0
Bank Sta=4995,4999
Exp/Cntr=0.3,0.1

Type RM Length L Ch R = 1,7262,462,462,462
BEGIN DESCRIPTION:
Stream0213 16.0
END DESCRIPTION:
XS GIS Cut Line= 3
      1858925.02     13948874.96      1858875.00     13948975.00
      1858824.99     13949125.03
#Sta/Elev= 30
  4888.6 1958.93  4891.4 1958.93  4897.0 1955.45  4902.6 1953.94  4911.0 1950.67
  4919.4 1946.35  4925.0 1944.62  4933.4 1940.47  4947.3 1935.11  4964.1 1927.48
  4969.7 1925.88  4978.1 1920.44  4986.5 1912.55  4992.1 1910.58  4995.7 1909.78
  4995.9 1909.28  4999.4 1909.28  4999.7 1909.78  5003.1 1909.78  5011.0 1911.20
  5042.6 1910.97  5053.2 1911.36  5063.7 1914.37  5074.2 1918.11  5095.3 1930.77
  5105.9 1936.26  5126.9 1949.98  5137.5 1955.43  5148.0 1958.20  5158.6 1958.69
#Mann=3,-1,0
  4888.6     0.1       0  4995.7    0.05       0  4999.7     0.1       0
Bank Sta=4995.7,4999.7
Exp/Cntr=0.3,0.1

Type RM Length L Ch R = 1,6800,444,444,444
BEGIN DESCRIPTION:
Stream0213 15.0
END DESCRIPTION:
XS GIS Cut Line= 4
      1858674.96     13948725.02      1858475.00     13948825.00
      1858375.00     13948925.00      1858277.10     13949125.26
#Sta/Elev= 30
  4776.2 1962.17  4798.5 1957.49  4820.9 1951.33  4829.3 1947.33  4834.9 1942.99
  4857.2 1932.35  4874.0 1926.24  4879.6 1922.81  4896.3 1917.06  4901.9 1913.31
  4924.3 1905.53  4941.1 1903.23  4963.4 1903.42  4995.0 1900.74  4995.2 1900.24
  4999.0 1900.74  5013.9 1901.22  5028.0 1906.99  5042.2 1913.95  5070.5 1930.41
  5084.6 1935.65  5112.9 1949.68  5129.5 1955.93  5137.7 1958.41  5144.0 1958.41
  5172.2 1966.61  5185.7 1969.35  5284.8 1971.93  5319.3 1976.59  5364.1 1978.73
#Mann=4,-1,0
  4776.2     0.1       0  4995.0    0.05       0  4999.0     0.1       0
  5129.5    0.07       0
Bank Sta=4995,4999
Exp/Cntr=0.3,0.1

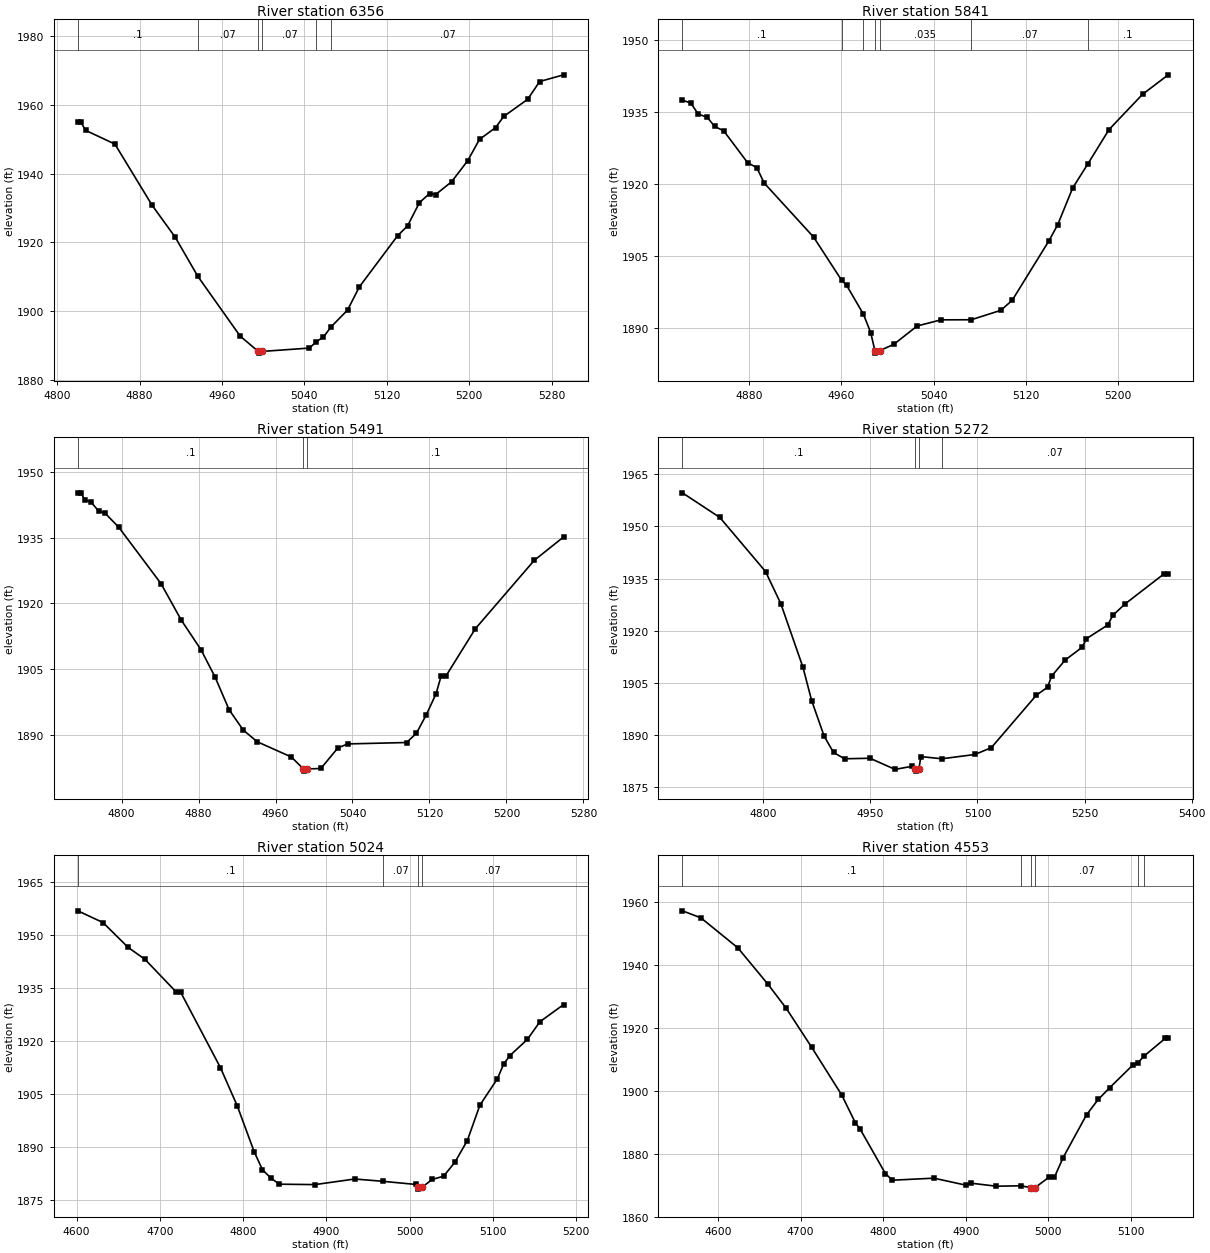
Type RM Length L Ch R = 1,6356,515,515,515
BEGIN DESCRIPTION:
Stream0213 14.0
END DESCRIPTION:
XS GIS Cut Line= 3
      1858374.96     13948375.03      1858225.00     13948475.00
      1858074.99     13948725.02
#Sta/Elev= 30
  4820.0 1954.94  4823.0 1954.94  4827.5 1952.59  4856.0 1948.59  4892.1 1930.83
  4914.6 1921.51  4936.5 1910.17  4977.7 1892.77  4995.2 1888.34  4995.5 1887.84
  4999.2 1888.34  5044.9 1889.31  5051.7 1891.18  5058.5 1892.50  5065.9 1895.47
  5081.9 1900.34  5093.5 1907.14  5130.5 1921.94  5140.2 1924.82  5151.8 1931.61
  5161.6 1934.22  5167.4 1933.91  5182.9 1937.62  5198.5 1943.71  5210.1 1949.97
  5225.7 1953.38  5233.5 1956.61  5256.8 1961.59  5268.5 1966.78  5291.8 1968.72
#Mann=6,-1,0
  4820.0     0.1       0  4936.5    0.07       0  4995.2    0.05       0
  4999.2    0.07       0  5051.7   0.035       0  5065.9    0.07       0
Bank Sta=4995.2,4999.2
Exp/Cntr=0.3,0.1

Type RM Length L Ch R = 1,5841,350,350,350
BEGIN DESCRIPTION:
Stream0213 13.0
END DESCRIPTION:
XS GIS Cut Line= 3
      1858025.01     13948024.99      1857891.26     13948136.33
      1857825.01     13948374.98
#Sta/Elev= 30
  4822.0 1937.40  4829.2 1936.84  4835.7 1934.53  4843.5 1933.86  4850.0 1931.95
  4857.8 1931.06  4878.6 1924.41  4886.5 1923.41  4893.0 1920.18  4935.9 1908.94
  4960.2 1899.97  4964.6 1898.89  4979.1 1892.92  4985.4 1889.10  4989.1 1885.32
  4989.3 1884.82  4993.1 1885.32  5005.5 1886.65  5025.8 1890.47  5046.5 1891.74
  5072.7 1891.76  5098.4 1893.72  5108.3 1895.82  5139.9 1908.08  5147.7 1911.49
  5160.7 1919.14  5173.8 1924.12  5192.3 1931.31  5221.4 1938.64  5243.7 1942.69
#Mann=7,-1,0
  4822.0     0.1       0  4960.2    0.07       0  4979.1   0.035       0
  4989.1   0.035       0  4993.1   0.035       0  5072.7    0.07       0
  5173.8     0.1       0
Bank Sta=4989.1,4993.1
Exp/Cntr=0.3,0.1

Type RM Length L Ch R = 1,5491,219,219,219
BEGIN DESCRIPTION:
Stream0213 12.0
END DESCRIPTION:
XS GIS Cut Line= 3
      1857825.01     13947774.99      1857625.00     13947925.00
      1857574.99     13948175.04
#Sta/Elev= 30
  4754.5 1945.26  4757.6 1945.26  4761.8 1943.66  4768.1 1943.18  4776.4 1941.03
  4782.6 1940.67  4797.2 1937.36  4841.0 1924.52  4861.8 1916.29  4882.6 1909.42
  4897.2 1903.19  4911.8 1895.73  4926.4 1891.12  4941.0 1888.44  4976.4 1884.97
  4989.0 1882.24  4989.2 1881.74  4993.0 1882.24  5007.1 1882.34  5024.9 1887.05
  5035.1 1887.95  5096.3 1888.27  5106.5 1890.41  5116.7 1894.59  5126.9 1899.43
  5132.0 1903.35  5137.1 1903.43  5167.7 1914.24  5228.9 1929.84  5259.5 1935.20
#Mann=3,-1,0
  4754.5     0.1       0  4989.0    0.05       0  4993.0     0.1       0
Bank Sta=4989,4993
Exp/Cntr=0.3,0.1

Type RM Length L Ch R = 1,5272,248,248,248
BEGIN DESCRIPTION:
Stream0213 11.1
END DESCRIPTION:
XS GIS Cut Line= 3
      1857769.96     13947589.99      1857468.42     13947771.95
      1857162.85     13947891.75
#Sta/Elev= 30
  4686.8 1959.66  4739.2 1952.58  4803.2 1937.04  4824.6 1927.80  4855.6 1909.53
  4867.8 1899.94  4885.3 1889.72  4898.4 1885.03  4913.9 1883.22  4949.5 1883.37
  4984.6 1880.17  5007.9 1881.04  5013.0 1880.17  5013.3 1879.67  5017.9 1880.17
  5020.7 1883.85  5050.1 1883.22  5096.4 1884.45  5119.5 1886.43  5182.3 1901.45
  5198.2 1903.80  5203.8 1906.95  5222.7 1911.57  5246.7 1915.29  5252.5 1917.72
  5282.3 1921.65  5289.7 1924.46  5306.7 1927.72  5361.0 1936.32  5367.2 1936.30
#Mann=4,-1,0
  4686.8     0.1       0  5013.0    0.05       0  5017.9     0.1       0
  5050.1    0.07       0
Bank Sta=5013,5017.9
Exp/Cntr=0.3,0.1

Type RM Length L Ch R = 1,5024,471,471,471
BEGIN DESCRIPTION:
Stream0213 11.0
END DESCRIPTION:
XS GIS Cut Line= 3
      1857725.02     13947525.00      1857325.00     13947575.00
      1857175.01     13947675.00
#Sta/Elev= 30
  4601.4 1956.93  4631.6 1953.61  4661.9 1946.55  4682.0 1943.19  4719.8 1933.86
  4724.9 1933.87  4772.7 1912.48  4792.9 1901.64  4813.1 1888.71  4823.1 1883.58
  4833.2 1881.22  4843.3 1879.48  4886.1 1879.36  4934.0 1880.95  4968.3 1880.28
  5007.5 1879.40  5009.6 1878.58  5009.9 1878.08  5014.5 1878.58  5027.1 1880.84
  5040.6 1881.74  5054.1 1885.66  5069.1 1891.83  5084.2 1901.86  5105.2 1909.33
  5112.7 1913.49  5120.2 1915.91  5141.2 1920.49  5156.3 1925.51  5184.8 1930.38
#Mann=4,-1,0
  4601.4     0.1       0  4968.3    0.07       0  5009.6    0.05       0
  5014.5    0.07       0
Bank Sta=5009.6,5014.5
Exp/Cntr=0.3,0.1

Type RM Length L Ch R = 1,4553,287,287,287
BEGIN DESCRIPTION:
Stream0213 10.0
END DESCRIPTION:
XS GIS Cut Line= 3
      1857425.03     13947024.99      1857025.00     13947225.00
      1856924.97     13947325.03
#Sta/Elev= 30
  4556.7 1957.14  4579.1 1954.91  4623.8 1945.40  4660.1 1933.91  4682.5 1926.19
  4713.3 1913.82  4749.6 1898.72  4766.4 1889.77  4772.0 1887.86  4802.7 1873.70
  4811.1 1871.60  4861.4 1872.25  4900.5 1870.01  4906.1 1870.67  4936.9 1869.70
  4966.4 1869.82  4979.1 1869.27  4979.5 1868.77  4984.1 1869.27  5001.1 1872.58
  5007.5 1872.58  5018.1 1878.81  5046.4 1892.38  5060.5 1897.23  5074.7 1901.04
  5102.9 1908.27  5108.3 1908.76  5115.9 1910.98  5141.8 1916.64  5145.4 1916.64
#Mann=6,-1,0
  4556.7     0.1       0  4966.4    0.07       0  4979.1    0.05       0
  4984.1    0.07       0  5108.3   0.035       0  5115.9    0.07       0
Bank Sta=4979.1,4984.1
Exp/Cntr=0.3,0.1

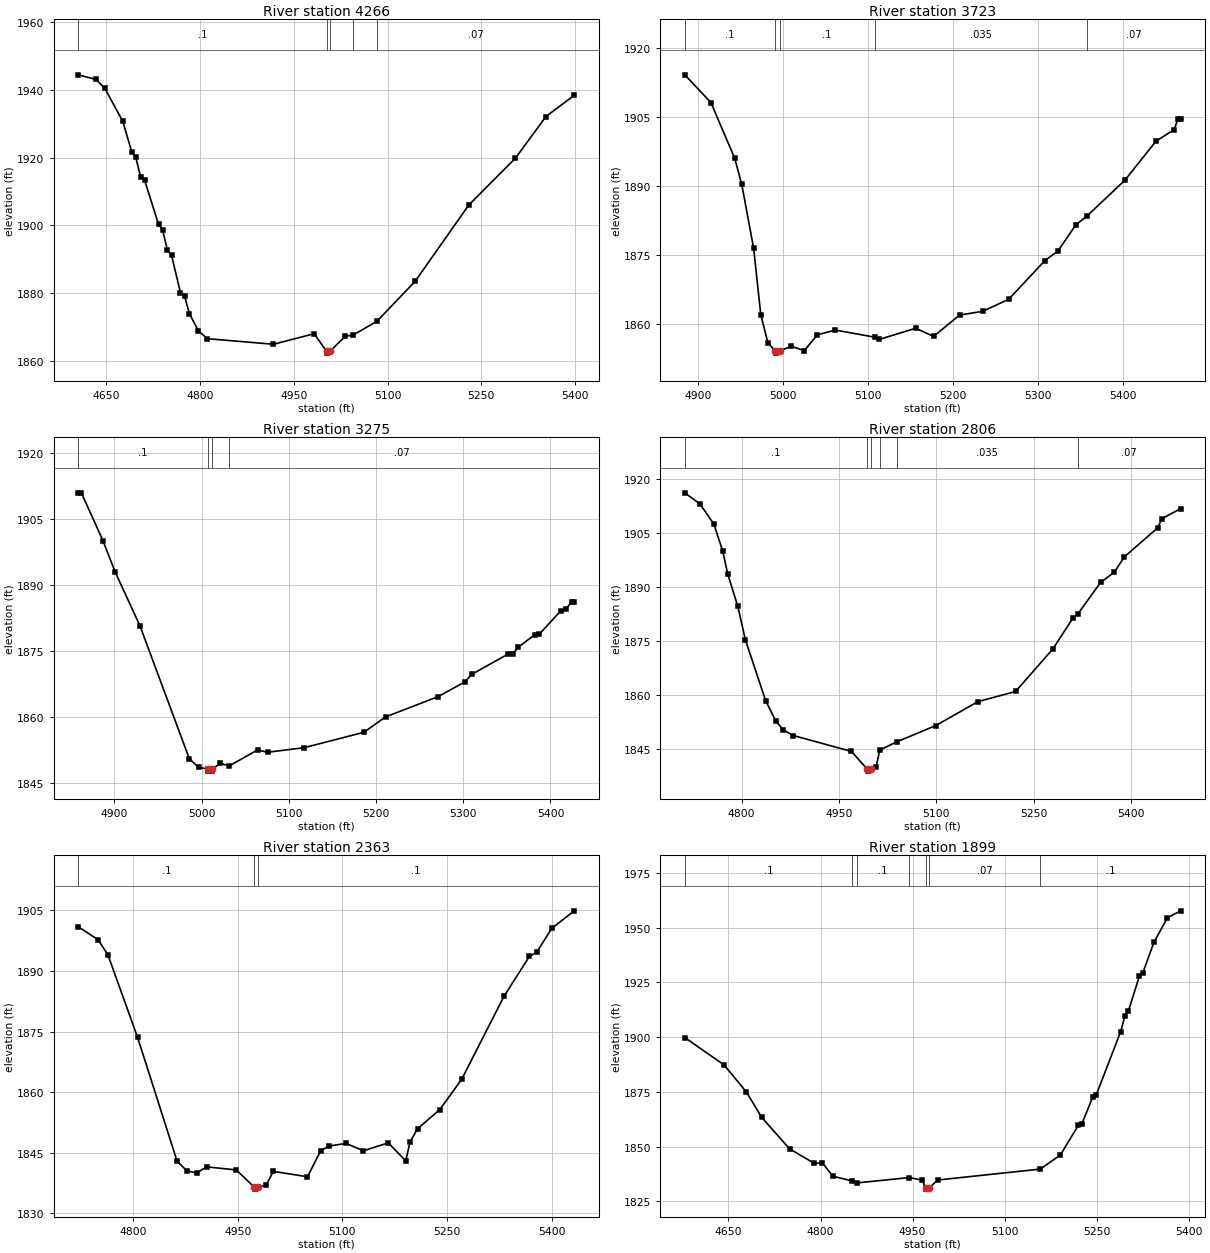
Type RM Length L Ch R = 1,4266,543,543,543
BEGIN DESCRIPTION:
Stream0213 9.0
END DESCRIPTION:
XS GIS Cut Line= 3
      1857225.01     13946724.99      1856938.94     13946962.91
      1856575.00     13947175.00
#Sta/Elev= 30
  4605.3 1944.50  4633.3 1943.15  4647.6 1940.51  4676.3 1930.80  4690.6 1921.83
  4697.1 1920.18  4704.9 1914.44  4711.4 1913.30  4733.6 1900.35  4740.1 1898.69
  4747.9 1892.62  4754.4 1891.17  4768.7 1880.12  4775.2 1879.10  4783.0 1873.93
  4797.4 1868.83  4811.7 1866.52  4917.5 1864.87  4982.6 1867.99  5002.6 1862.75
  5003.0 1862.25  5007.6 1862.75  5032.6 1867.27  5044.7 1867.55  5083.1 1871.68
  5144.0 1883.43  5230.3 1906.08  5304.7 1919.88  5353.5 1932.18  5398.6 1938.42
#Mann=5,-1,0
  4605.3     0.1       0  5002.6    0.05       0  5007.6     0.1       0
  5044.7   0.035       0  5083.1    0.07       0
Bank Sta=5002.6,5007.6
Exp/Cntr=0.3,0.1

Type RM Length L Ch R = 1,3723,448,448,448
BEGIN DESCRIPTION:
Stream0213 8.0
END DESCRIPTION:
XS GIS Cut Line= 3
      1856774.98     13946425.03      1856725.00     13946525.00
      1856474.98     13946925.03
#Sta/Elev= 30
  4884.0 1914.19  4914.7 1908.16  4942.7 1896.03  4951.0 1890.35  4965.0 1876.40
  4973.4 1861.95  4981.8 1855.80  4990.4 1854.06  4990.8 1853.56  4995.5 1854.06
  5009.3 1855.04  5024.7 1854.12  5040.0 1857.55  5061.2 1858.58  5107.7 1857.03
  5113.1 1856.56  5155.6 1858.97  5176.8 1857.21  5207.4 1861.86  5234.6 1862.66
  5265.2 1865.30  5307.7 1873.70  5323.0 1875.79  5344.2 1881.50  5357.1 1883.39
  5402.0 1891.25  5438.6 1899.75  5459.8 1902.24  5464.5 1904.61  5467.5 1904.61
#Mann=5,-1,0
  4884.0     0.1       0  4990.4    0.05       0  4995.5     0.1       0
  5107.7   0.035       0  5357.1    0.07       0
Bank Sta=4990.4,4995.5
Exp/Cntr=0.3,0.1

Type RM Length L Ch R = 1,3275,469,469,469
BEGIN DESCRIPTION:
Stream0213 7.0
END DESCRIPTION:
XS GIS Cut Line= 3
      1856424.98     13946275.02      1856325.00     13946375.00
      1856175.00     13946775.00
#Sta/Elev= 30
  4858.6 1910.92  4862.1 1910.92  4886.9 1900.00  4901.0 1892.85  4929.3 1880.66
  4985.9 1850.43  4996.5 1848.47  5007.2 1848.12  5007.6 1847.62  5011.9 1847.62
  5012.3 1848.12  5021.4 1849.36  5031.8 1848.83  5064.1 1852.43  5075.6 1851.91
  5117.5 1852.95  5186.0 1856.45  5210.9 1859.95  5271.4 1864.58  5301.7 1867.91
  5309.7 1869.62  5351.5 1874.26  5356.9 1874.34  5363.1 1875.80  5381.8 1878.62
  5387.2 1878.76  5412.1 1884.13  5417.4 1884.41  5424.5 1886.19  5427.2 1886.19
#Mann=4,-1,0
  4858.6     0.1       0  5007.2    0.05       0  5012.3     0.1       0
  5031.8    0.07       0
Bank Sta=5007.2,5012.3
Exp/Cntr=0.3,0.1

Type RM Length L Ch R = 1,2806,443,443,443
BEGIN DESCRIPTION:
Stream0213 6.0
END DESCRIPTION:
XS GIS Cut Line= 3
      1856074.99     13945925.02      1855925.00     13946175.00
      1855675.01     13946574.98
#Sta/Elev= 30
  4712.7 1916.12  4736.0 1913.03  4757.4 1907.44  4771.0 1899.96  4778.8 1893.54
  4794.3 1884.53  4806.0 1875.21  4837.1 1858.34  4852.6 1852.70  4864.3 1850.14
  4879.8 1848.61  4969.2 1844.19  4993.8 1839.21  4994.2 1838.71  4999.1 1839.21
  5007.2 1839.89  5012.7 1844.56  5039.3 1846.89  5098.6 1851.34  5164.0 1858.05
  5221.8 1860.86  5279.6 1872.77  5310.2 1881.32  5317.3 1882.33  5352.7 1891.19
  5373.9 1894.05  5389.3 1898.32  5440.6 1906.38  5447.0 1908.94  5475.9 1911.71
#Mann=6,-1,0
  4712.7     0.1       0  4993.8    0.05       0  4999.1     0.1       0
  5012.7    0.07       0  5039.3   0.035       0  5317.3    0.07       0
Bank Sta=4993.8,4999.1
Exp/Cntr=0.3,0.1

Type RM Length L Ch R = 1,2363,464,464,464
BEGIN DESCRIPTION:
Stream0213 5.0
END DESCRIPTION:
XS GIS Cut Line= 3
      1855775.01     13945724.99      1855575.00     13945925.00
      1855174.96     13946075.02
#Sta/Elev= 30
  4721.8 1900.95  4750.1 1897.75  4764.2 1894.00  4806.7 1873.52  4863.2 1842.88
  4877.4 1840.44  4891.5 1839.99  4905.7 1841.46  4948.1 1840.69  4973.7 1836.44
  4974.1 1835.94  4979.0 1836.44  4990.5 1836.87  5001.1 1840.34  5050.0 1839.00
  5068.7 1845.39  5080.3 1846.60  5105.2 1847.27  5130.1 1845.44  5165.7 1847.41
  5190.7 1842.94  5196.9 1847.66  5207.6 1850.90  5239.6 1855.67  5270.8 1863.15
  5331.3 1883.69  5367.8 1893.62  5378.5 1894.71  5399.8 1900.55  5431.9 1904.91
#Mann=3,-1,0
  4721.8     0.1       0  4973.7    0.05       0  4979.0     0.1       0
Bank Sta=4973.7,4979
Exp/Cntr=0.3,0.1

Type RM Length L Ch R = 1,1899,490,490,490
BEGIN DESCRIPTION:
Stream0213 4.0
END DESCRIPTION:
XS GIS Cut Line= 3
      1855774.96     13945674.98      1855375.00     13945525.00
      1855025.04     13945375.02
#Sta/Elev= 30
  4578.8 1899.76  4642.8 1887.27  4679.3 1874.86  4704.2 1863.29  4749.6 1848.94
  4789.7 1842.35  4803.0 1842.54  4819.9 1836.46  4851.9 1834.27  4859.6 1833.41
  4944.7 1835.84  4965.9 1834.65  4971.2 1831.06  4971.6 1830.56  4976.7 1831.06
  4990.8 1834.72  5158.1 1839.71  5190.9 1846.19  5219.9 1859.62  5225.4 1860.12
  5243.5 1872.58  5248.9 1873.35  5288.8 1902.35  5296.1 1909.74  5301.5 1911.77
  5319.6 1927.93  5325.1 1929.35  5343.2 1943.22  5365.0 1954.44  5386.7 1957.64
#Mann=7,-1,0
  4578.8     0.1       0  4851.9    0.07       0  4859.6     0.1       0
  4944.7    0.07       0  4971.2    0.05       0  4976.7    0.07       0
  5158.1     0.1       0
Bank Sta=4971.2,4976.7
Exp/Cntr=0.3,0.1

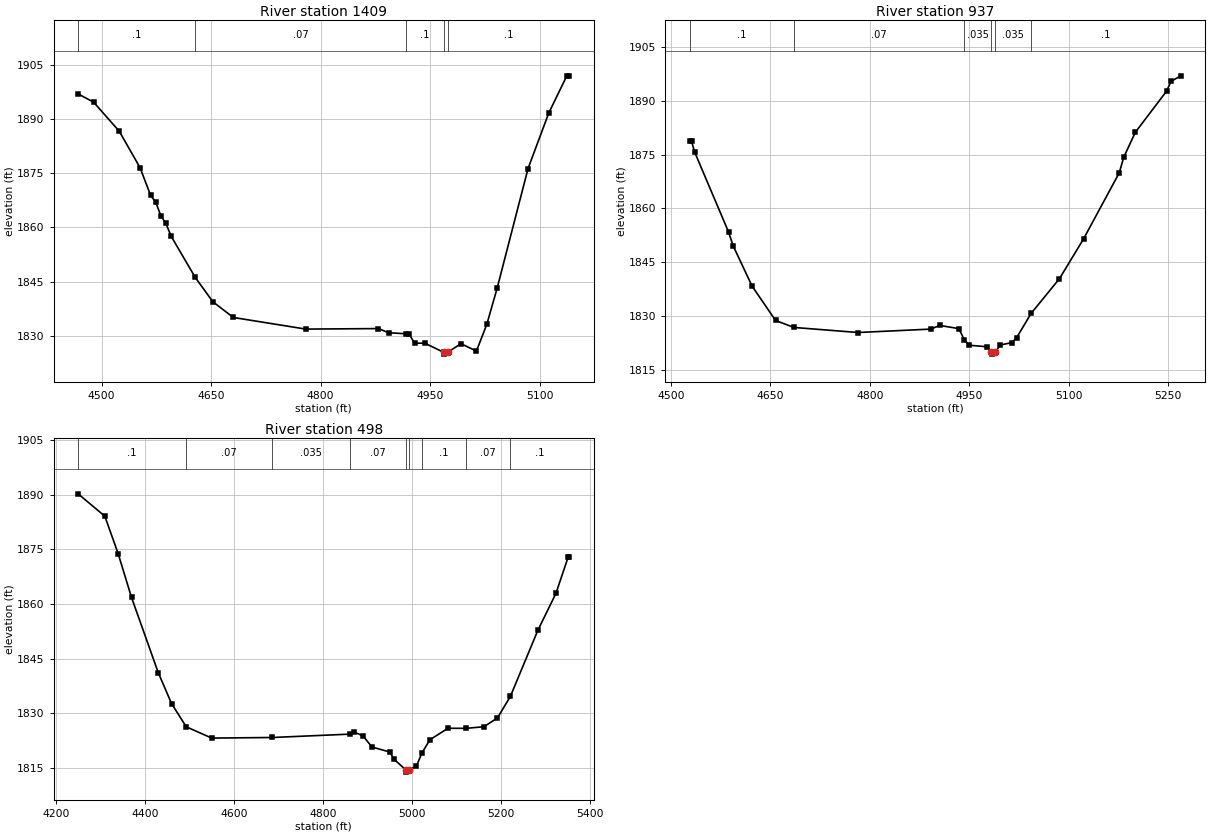
Type RM Length L Ch R = 1,1409,472,472,472
BEGIN DESCRIPTION:
Stream0213 3.0
END DESCRIPTION:
XS GIS Cut Line= 3
      1855874.98     13945424.98      1855475.00     13945075.00
      1855375.00     13944975.00
#Sta/Elev= 30
  4467.9 1896.92  4489.2 1894.62  4524.3 1886.59  4552.8 1876.50  4567.1 1868.92
  4574.2 1867.00  4581.3 1863.21  4587.9 1861.20  4595.5 1857.52  4628.3 1846.20
  4652.5 1839.46  4680.5 1835.12  4779.7 1831.91  4879.3 1832.05  4893.1 1830.90
  4917.3 1830.62  4921.1 1830.59  4928.7 1828.03  4942.9 1828.01  4968.6 1825.49
  4969.0 1824.99  4974.2 1825.49  4992.3 1827.88  5013.5 1825.83  5027.7 1833.22
  5041.8 1843.17  5084.2 1876.28  5112.5 1891.60  5137.3 1901.91  5140.8 1901.91
#Mann=5,-1,0
  4467.9     0.1       0  4628.3    0.07       0  4917.3     0.1       0
  4968.6    0.05       0  4974.2     0.1       0
Bank Sta=4968.6,4974.2
Exp/Cntr=0.3,0.1

Type RM Length L Ch R = 1,937,439,439,439
BEGIN DESCRIPTION:
Stream0213 2.0
END DESCRIPTION:
XS GIS Cut Line= 3
      1856025.00     13945125.01      1855775.00     13944725.00
      1855524.97     13944624.99
#Sta/Elev= 30
  4528.3 1878.67  4531.3 1878.67  4536.0 1875.68  4587.3 1853.35  4593.8 1849.67
  4622.6 1838.37  4658.0 1828.81  4685.6 1826.87  4782.4 1825.46  4892.1 1826.41
  4905.7 1827.43  4934.6 1826.53  4942.4 1823.50  4949.9 1821.92  4977.0 1821.49
  4983.6 1819.94  4984.1 1819.44  4989.2 1819.94  4997.1 1821.98  5014.8 1822.67
  5021.5 1823.99  5043.5 1830.79  5086.2 1840.45  5122.5 1851.51  5176.4 1869.93
  5183.1 1874.23  5200.6 1881.19  5247.7 1892.65  5254.5 1895.40  5269.3 1896.93
#Mann=6,-1,0
  4528.3     0.1       0  4685.6    0.07       0  4942.4   0.035       0
  4983.6   0.035       0  4989.2   0.035       0  5043.5     0.1       0
Bank Sta=4983.6,4989.2
Exp/Cntr=0.3,0.1

Type RM Length L Ch R = 1,498,0,0,0
BEGIN DESCRIPTION:
Stream0213 1.0
END DESCRIPTION:
XS GIS Cut Line= 3
      1856075.00     13945174.97      1856075.00     13944425.00
      1855725.02     13944375.00
#Sta/Elev= 30
  4249.7 1890.32  4309.7 1884.17  4339.7 1873.84  4369.7 1861.79  4429.7 1841.12
  4459.7 1832.57  4492.6 1826.21  4549.7 1823.10  4685.8 1823.26  4861.0 1824.19
  4869.7 1824.76  4889.7 1823.71  4909.7 1820.64  4949.7 1819.27  4959.7 1817.23
  4986.9 1814.23  4987.3 1813.73  4992.5 1814.23  5009.8 1815.46  5022.4 1819.10
  5040.1 1822.66  5080.5 1825.80  5121.5 1825.78  5161.3 1826.23  5191.6 1828.63
  5220.6 1834.55  5282.5 1852.78  5322.9 1862.89  5350.7 1872.99  5353.2 1872.99
#Mann=9,-1,0
  4249.7     0.1       0  4492.6    0.07       0  4685.8   0.035       0
  4861.0    0.07       0  4986.9    0.05       0  4992.5    0.07       0
  5022.4     0.1       0  5121.5    0.07       0  5220.6     0.1       0
Bank Sta=4986.9,4992.5
Exp/Cntr=0.3,0.1

Chan Stop Cuts=-1