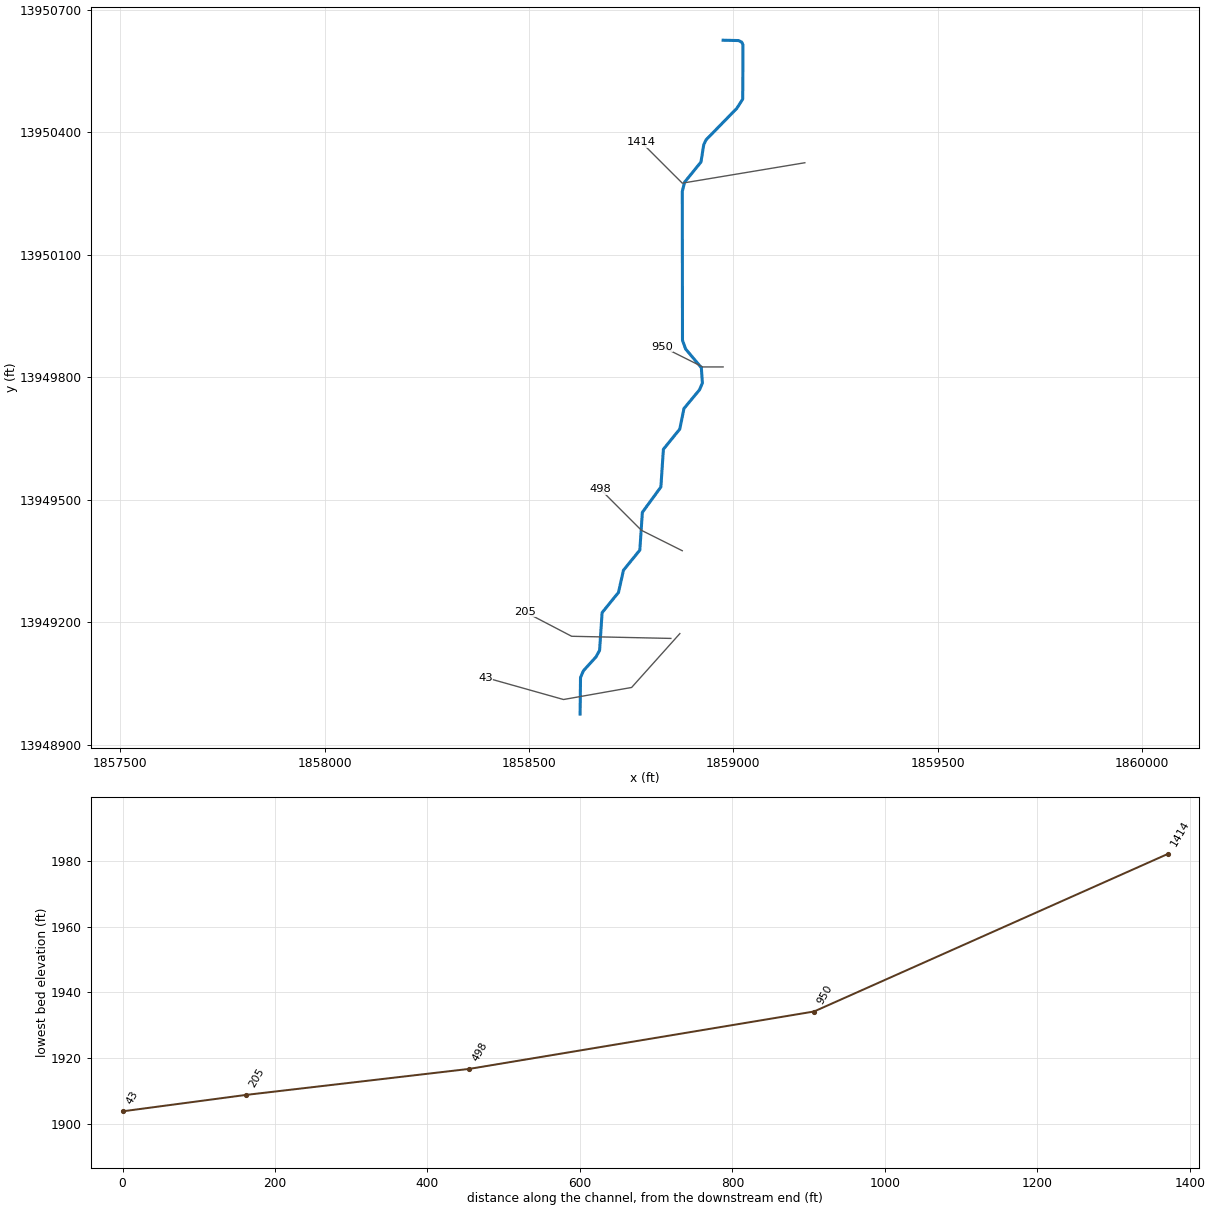
--- Stream0214.prj (project) ---

Proj Title=Stream0214 Base Level Engineering
Current Plan=p01
Default Exp/Contr=0.3,0.1
English Units
Geom File=g01
Flow File=f01
Plan File=p01
Y Axis Title=Elevation
X Axis Title(PF)=Main Channel Distance
X Axis Title(XS)=Station
BEGIN DESCRIPTION:
Stream0214
END DESCRIPTION:
DSS Export Rating Curves= 0
DSS Export Rating Curve Sorted= 0
DSS Export Volume Flow Curves= 0
DXF OffsetX= 0
DXF OffsetY= 0
DXF ScaleX= 1
DXF ScaleY= 10

--- Stream0214.p01 (plan) ---

Plan Title=Multiple Run
Short Identifier=Multiple
Geom File=g01
Flow File=f01
Subcritical Flow
K Sum by GR= 0
Std Step Tol= 0.01
Critical Tol= 0.01
Num of Std Step Trials= 20
Max Error Tol= 0.3
Flow Tol Ratio= 0.001
Split Flow NTrial= 30
Split Flow Tol= 0.02
Split Flow Ratio= 0.02
Log Output Level= 0
Friction Slope Method= 1
Unsteady Friction Slope Method= 2
Unsteady Bridges Friction Slope Method= 1
Parabolic Critical Depth
Global Vel Dist=  1 , 1 , 1
Global Log Level= 0
CheckData=True
Encroach Param= -1, 0, 0, 0
BEGIN DESCRIPTION:
Multiple Run
END DESCRIPTION:

--- Stream0214.f01 (steady flow) ---

Flow Title=Multiple
Program Version=4.10
Number of Profiles= 7
Profile Names=10-year,25-year,50-year,1pct_min,100-year,1pct_plu,500-year
River Rch & RM=Stream0214,Reach-1         ,1414
     615    1015    1385     916    1828    3648    3141
Boundary for River Rch & Prof#=Stream0214,Reach-1         , 1
Up Type= 0
Dn Type= 3
Dn Slope=0.005
Boundary for River Rch & Prof#=Stream0214,Reach-1         , 2
Up Type= 0
Dn Type= 3
Dn Slope=0.005
Boundary for River Rch & Prof#=Stream0214,Reach-1         , 3
Up Type= 0
Dn Type= 3
Dn Slope=0.005
Boundary for River Rch & Prof#=Stream0214,Reach-1         , 4
Up Type= 0
Dn Type= 3
Dn Slope=0.005
Boundary for River Rch & Prof#=Stream0214,Reach-1         , 5
Up Type= 0
Dn Type= 3
Dn Slope=0.005
Boundary for River Rch & Prof#=Stream0214,Reach-1         , 6
Up Type= 0
Dn Type= 3
Dn Slope=0.005
Boundary for River Rch & Prof#=Stream0214,Reach-1         , 7
Up Type= 0
Dn Type= 3
Dn Slope=0.005
DSS Import GetInterval= 0
DSS Import GetPeak= 0
DSS Import FillOption= 0

--- Stream0214.g01 (geometry) ---

Geom Title=Existing Conditions
Program Version=4.10

River Reach=Stream0214      ,Reach-1
Reach XY= 30
        1858975.       13950625.      1859012.57     13950624.16
      1859020.38     13950620.37      1859023.59     13950613.56
      1859022.95     13950480.86      1859008.54     13950458.25
      1858933.16     13950381.05       1858927.5     13950368.96
      1858920.78     13950326.75      1858880.71     13950277.35
      1858875.06     13950254.97      1858875.54     13949890.21
      1858883.19     13949868.92      1858921.63     13949823.26
      1858924.25     13949785.68      1858917.23     13949769.06
      1858879.22     13949723.28      1858868.89     13949672.82
      1858828.83     13949623.42      1858822.65     13949530.97
      1858777.35     13949469.03      1858771.17     13949376.58
      1858731.11     13949327.18      1858718.89     13949272.82
      1858678.83     13949223.42      1858672.67     13949130.97
      1858664.16     13949115.35      1858633.11     13949081.07
      1858626.02     13949064.58        1858625.       13948975.

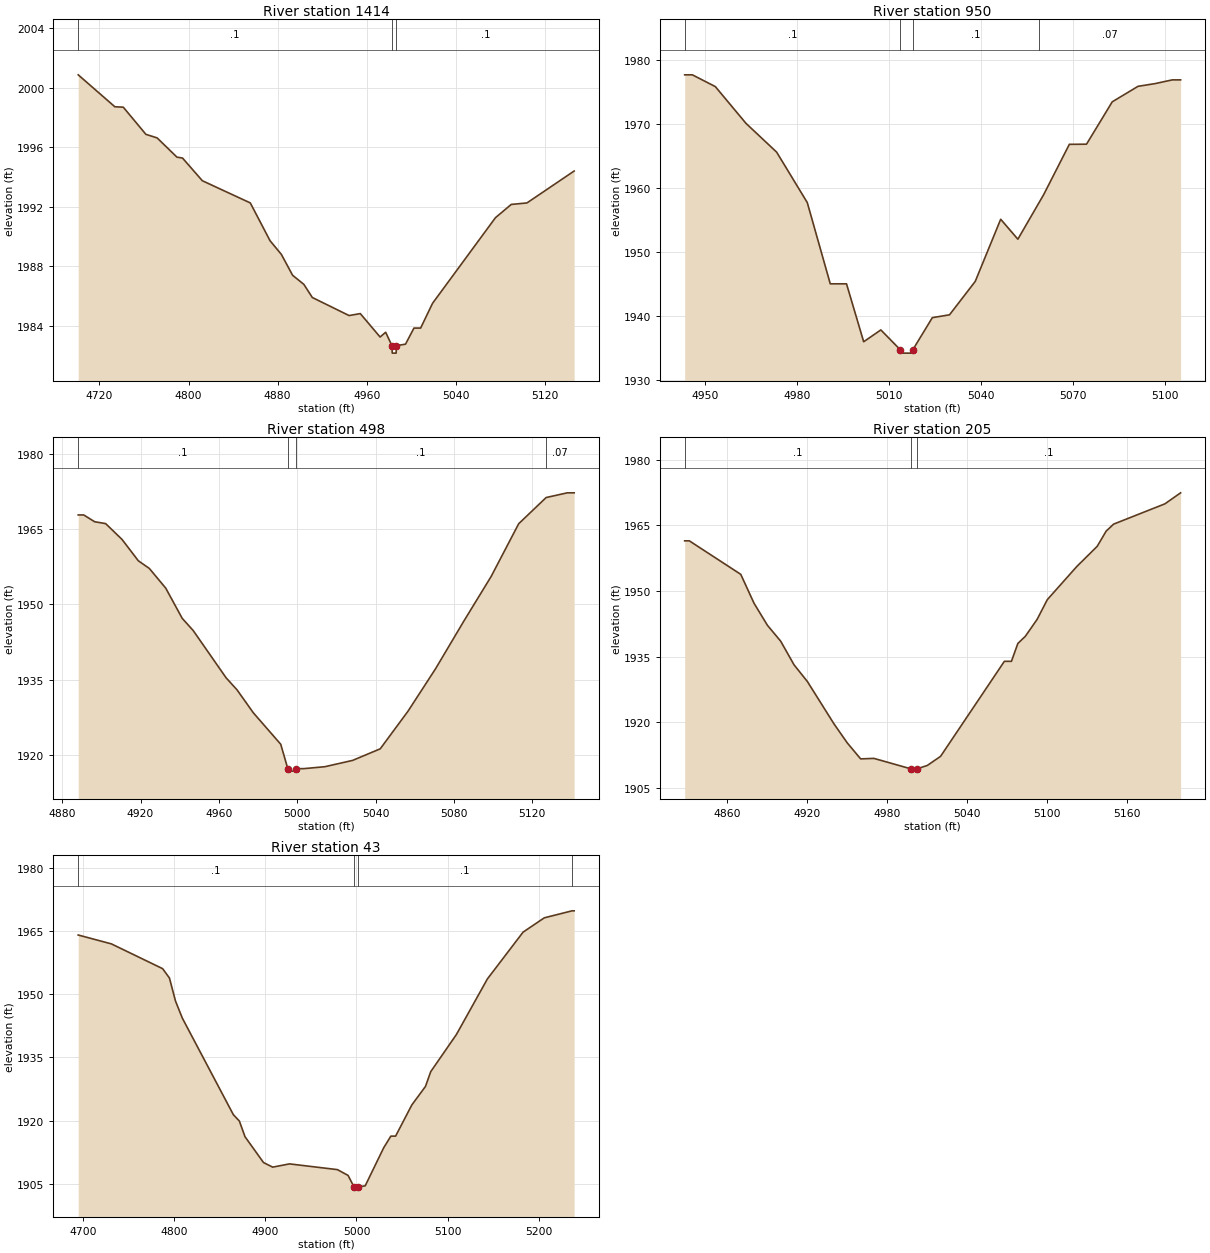
Type RM Length L Ch R = 1 ,1414    ,464,464,464
BEGIN DESCRIPTION:
Stream0214 3.0
END DESCRIPTION:
XS GIS Cut Line= 3
      1859174.97       13950325.        1858875.       13950275.
      1858775.02     13950374.98
#Sta/Elev= 30
  4700.9 2000.85  4733.8 1998.71  4741.4 1998.68  4761.7 1996.86  4771.8 1996.62
  4789.6 1995.33  4794.6 1995.27  4812.4 1993.75  4855.5 1992.26  4873.2 1989.73
  4883.4 1988.81  4893.5 1987.41  4903.6  1986.8  4911.2 1985.92  4944.2 1984.71
  4954.3 1984.84  4972.1 1983.27  4977.1 1983.59  4982.7 1982.69    4983 1982.19
  4986.5 1982.19  4986.7 1982.69  4994.9 1982.79  5002.5 1983.87  5008.5 1983.87
  5019.2 1985.53  5075.7 1991.27  5089.9 1992.16    5104 1992.26  5146.4  1994.4
#Mann= 3 ,-1 , 0
  4700.9      .1       0  4982.7     .05       0  4986.7      .1       0
Bank Sta=4982.7,4986.7
XS Rating Curve= 0 ,0
Exp/Cntr=0.3,0.1

Type RM Length L Ch R = 1 ,950     ,452,452,452
BEGIN DESCRIPTION:
Stream0214 2.0
END DESCRIPTION:
XS GIS Cut Line= 3
      1858975.04       13949825.        1858925.       13949825.
      1858825.04     13949874.98
#Sta/Elev= 29
  4943.4 1977.74  4945.9 1977.74  4953.4  1975.9  4963.4 1970.15  4973.4 1965.65
  4983.4 1957.76  4990.9 1945.05  4993.4 1945.05  4996.2 1945.05  5001.8 1935.99
  5007.4 1937.84  5013.8 1934.71  5014.1 1934.21  5017.6 1934.21  5017.8 1934.71
  5024.2 1939.76  5029.8  1940.2  5038.2 1945.43  5046.5 1955.15  5052.1 1952.03
    5059 1957.74  5060.5 1958.98  5068.9 1966.87  5074.5 1966.89  5082.9 1973.52
  5091.3 1975.94  5096.9 1976.37  5102.5 1976.95  5105.2 1976.95
#Mann= 4 ,-1 , 0
  4943.4      .1       0  5013.8     .05       0  5017.8      .1       0
    5059     .07       0
Bank Sta=5013.8,5017.8
XS Rating Curve= 0 ,0
Exp/Cntr=0.3,0.1

Type RM Length L Ch R = 1 ,498     ,293,293,293
BEGIN DESCRIPTION:
Stream0214 1.0
END DESCRIPTION:
XS GIS Cut Line= 3
        1858875.       13949375.        1858775.       13949425.
      1858675.02     13949524.98
#Sta/Elev= 30
  4888.2 1967.85    4891 1967.85  4896.6 1966.49  4902.2 1966.12  4910.6 1962.95
  4918.9  1958.7  4924.5 1957.18  4932.9 1953.24  4941.3 1947.22  4946.9 1944.79
  4963.7 1935.36  4969.3 1932.95  4977.6 1928.38  4991.6  1922.1  4995.2 1917.24
  4995.5 1916.74    4999 1916.74  4999.2 1917.24  5003.5 1917.24  5014.1 1917.62
  5028.3 1918.88  5042.4 1921.19  5056.6 1928.71  5070.7  1937.2  5084.9 1946.55
    5099 1955.56  5113.1  1966.1  5127.1 1971.32  5137.9 1972.26  5141.4 1972.26
#Mann= 4 ,-1 , 0
  4888.2      .1       0  4995.2     .05       0  4999.2      .1       0
  5127.1     .07       0
Bank Sta=4995.2,4999.2
XS Rating Curve= 0 ,0
Exp/Cntr=0.3,0.1

Type RM Length L Ch R = 1 ,205     ,162,162,162
BEGIN DESCRIPTION:
Stream0214 0.0
END DESCRIPTION:
XS GIS Cut Line= 3
      1858847.07     13949160.26      1858604.29     13949165.52
      1858489.51     13949225.42
#Sta/Elev= 30
    4828 1961.47  4831.5 1961.47  4870.1 1953.81  4880.1 1947.18  4890.1 1942.17
  4900.1 1938.51  4910.1 1933.12  4920.1 1929.31  4940.1 1919.61  4950.1 1915.25
  4960.1 1911.61  4970.1 1911.72  4998.1 1909.31  4998.4 1908.81  5001.9 1908.81
  5002.1 1909.31  5010.1  1910.1  5020.1 1912.19    5068 1933.92  5073.3 1933.92
  5078.1    1938  5083.7 1939.63  5092.6 1943.52  5100.2 1948.01  5122.3 1955.58
  5137.7 1960.22  5144.4 1963.69    5150 1965.29  5188.5 1969.93  5200.3 1972.45
#Mann= 3 ,-1 , 0
    4828      .1       0  4998.1     .05       0  5002.1      .1       0
Bank Sta=4998.1,5002.1
XS Rating Curve= 0 ,0
Exp/Cntr=0.3,0.1

Type RM Length L Ch R = 1 ,43      ,0,0,0
BEGIN DESCRIPTION:
Stream0214 0.1
END DESCRIPTION:
XS GIS Cut Line= 4
       1858869.1      13949172.1      1858751.06     13949040.18
      1858584.39     13949010.66      1858393.42     13949064.48
#Sta/Elev= 30
  4694.4 1964.02  4730.8 1961.92  4787.1 1956.05  4794.6 1953.83  4801.3 1948.34
  4808.8 1944.31  4864.8 1921.45  4871.4 1919.94  4877.6 1916.23  4897.9 1910.11
    4908 1909.02  4926.5 1909.79  4979.1 1908.43  4990.8 1907.06  4997.4 1904.31
  4997.7 1903.81  5001.4 1904.31  5009.6 1904.59  5029.9  1913.6  5037.8 1916.37
    5043 1916.37  5060.8 1923.75  5075.8 1928.14  5081.6 1931.65  5109.8 1940.45
  5143.8 1953.61    5183  1964.7  5206.3 1968.09  5236.8 1969.75  5239.1 1969.75
#Mann= 4 ,-1 , 0
  4694.4      .1       0  4997.4     .05       0  5001.4      .1       0
  5236.8     .07       0
Bank Sta=4997.4,5001.4
XS Rating Curve= 0 ,0
Exp/Cntr=0.3,0.1

Chan Stop Cuts=-1
Use User Specified Reach Order=0
Composite Channel Slope=5