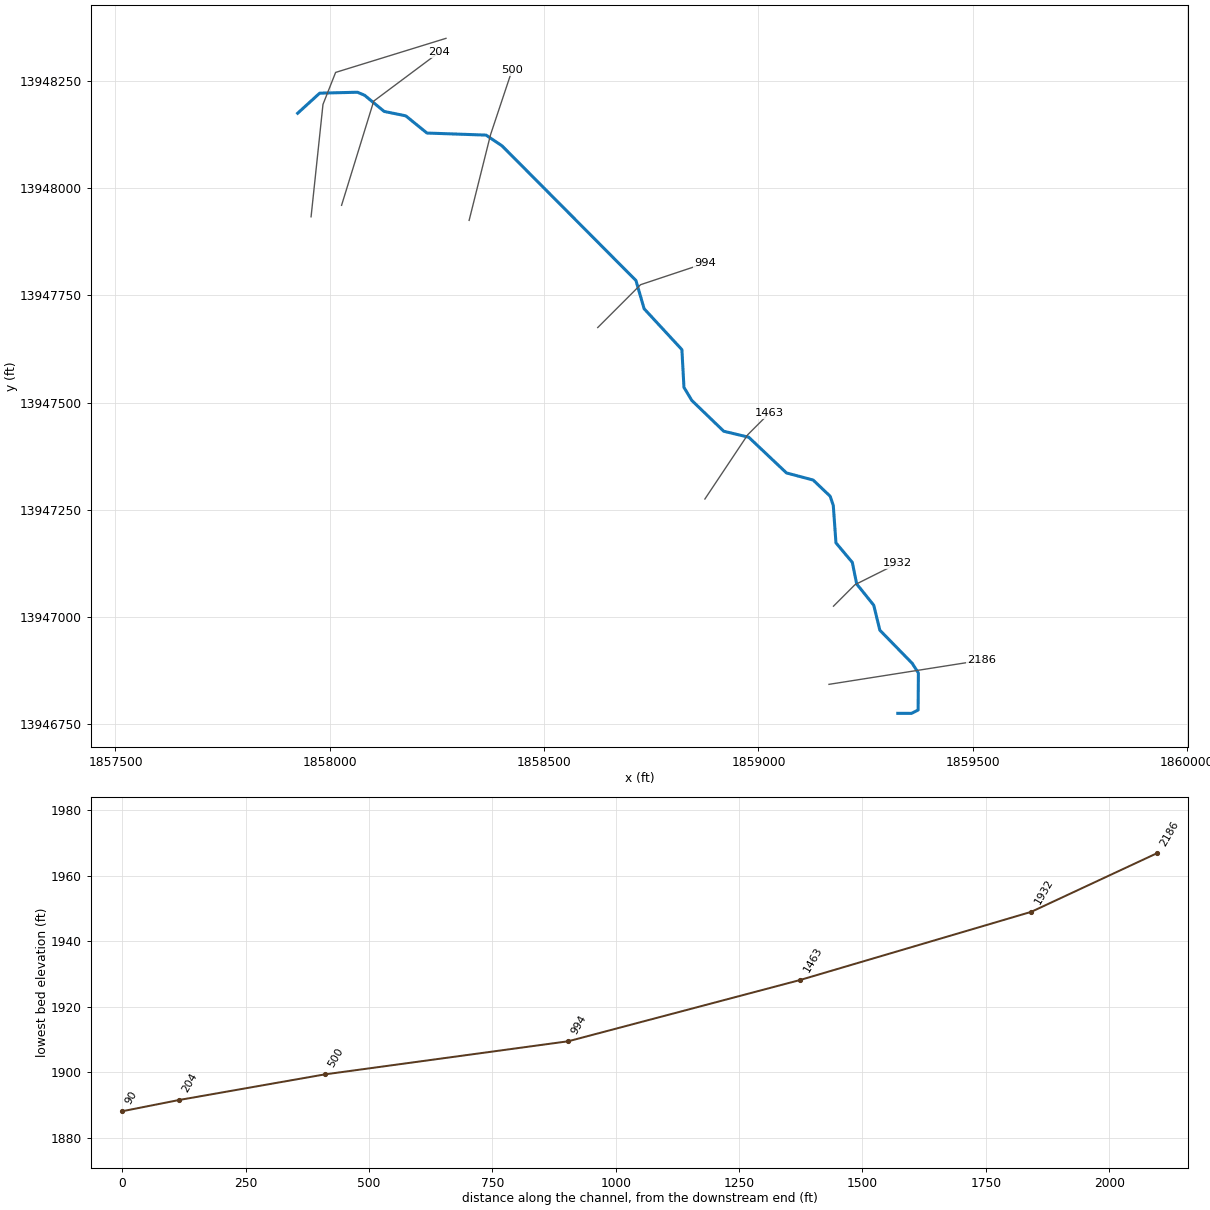
--- Stream0215.prj (project) ---

Proj Title=Stream0215 Base Level Engineering
Current Plan=p01
Default Exp/Contr=0.3,0.1
English Units
Geom File=g01
Flow File=f01
Plan File=p01
Y Axis Title=Elevation
X Axis Title(PF)=Main Channel Distance
X Axis Title(XS)=Station
BEGIN DESCRIPTION:
Stream0215
END DESCRIPTION:
DSS Export Rating Curves= 0
DSS Export Rating Curve Sorted= 0
DSS Export Volume Flow Curves= 0
DXF OffsetX= 0
DXF OffsetY= 0
DXF ScaleX= 1
DXF ScaleY= 10

--- Stream0215.p01 (plan) ---

Plan Title=Multiple Run
Short Identifier=Multiple
Geom File=g01
Flow File=f01
Subcritical Flow
K Sum by GR= 0
Std Step Tol= 0.01
Critical Tol= 0.01
Num of Std Step Trials= 20
Max Error Tol= 0.3
Flow Tol Ratio= 0.001
Split Flow NTrial= 30
Split Flow Tol= 0.02
Split Flow Ratio= 0.02
Log Output Level= 0
Friction Slope Method= 1
Unsteady Friction Slope Method= 2
Unsteady Bridges Friction Slope Method= 1
Parabolic Critical Depth
Global Vel Dist=  1 , 1 , 1
Global Log Level= 0
CheckData=True
Encroach Param= -1, 0, 0, 0
BEGIN DESCRIPTION:
Multiple Run
END DESCRIPTION:

--- Stream0215.f01 (steady flow) ---

Flow Title=Multiple
Program Version=4.10
Number of Profiles= 7
Profile Names=10-year,25-year,50-year,1pct_min,100-year,1pct_plu,500-year
River Rch & RM=Stream0215,Reach-1         ,2186
     482     784    1060     696    1389    2772    2348
Boundary for River Rch & Prof#=Stream0215,Reach-1         , 1
Up Type= 0
Dn Type= 3
Dn Slope=0.005
Boundary for River Rch & Prof#=Stream0215,Reach-1         , 2
Up Type= 0
Dn Type= 3
Dn Slope=0.005
Boundary for River Rch & Prof#=Stream0215,Reach-1         , 3
Up Type= 0
Dn Type= 3
Dn Slope=0.005
Boundary for River Rch & Prof#=Stream0215,Reach-1         , 4
Up Type= 0
Dn Type= 3
Dn Slope=0.005
Boundary for River Rch & Prof#=Stream0215,Reach-1         , 5
Up Type= 0
Dn Type= 3
Dn Slope=0.005
Boundary for River Rch & Prof#=Stream0215,Reach-1         , 6
Up Type= 0
Dn Type= 3
Dn Slope=0.005
Boundary for River Rch & Prof#=Stream0215,Reach-1         , 7
Up Type= 0
Dn Type= 3
Dn Slope=0.005
DSS Import GetInterval= 0
DSS Import GetPeak= 0
DSS Import FillOption= 0

--- Stream0215.g01 (geometry) ---

Geom Title=Existing Conditions
Program Version=4.10

River Reach=Stream0215      ,Reach-1
Reach XY= 30
        1859325.       13946775.      1859357.01     13946774.92
      1859372.44     13946782.76      1859373.08     13946869.07
      1859358.57     13946891.73      1859283.16     13946968.95
       1859268.9     13947027.19      1859229.16     13947076.72
      1859218.88     13947127.18      1859180.77     13947172.68
      1859174.53     13947259.91      1859167.26     13947281.45
      1859127.57     13947319.26      1859065.35     13947335.81
      1858977.28     13947419.13      1858918.93     13947433.15
      1858844.61      13947504.8      1858826.16     13947535.48
      1858821.37      13947623.5      1858733.18     13947718.96
      1858714.22     13947784.68      1858401.87     13948098.83
      1858364.56     13948123.94      1858226.56     13948128.76
      1858177.18     13948168.88      1858126.73     13948179.19
      1858081.06     13948216.96      1858064.47     13948223.93
       1857976.4     13948221.81        1857925.       13948175.

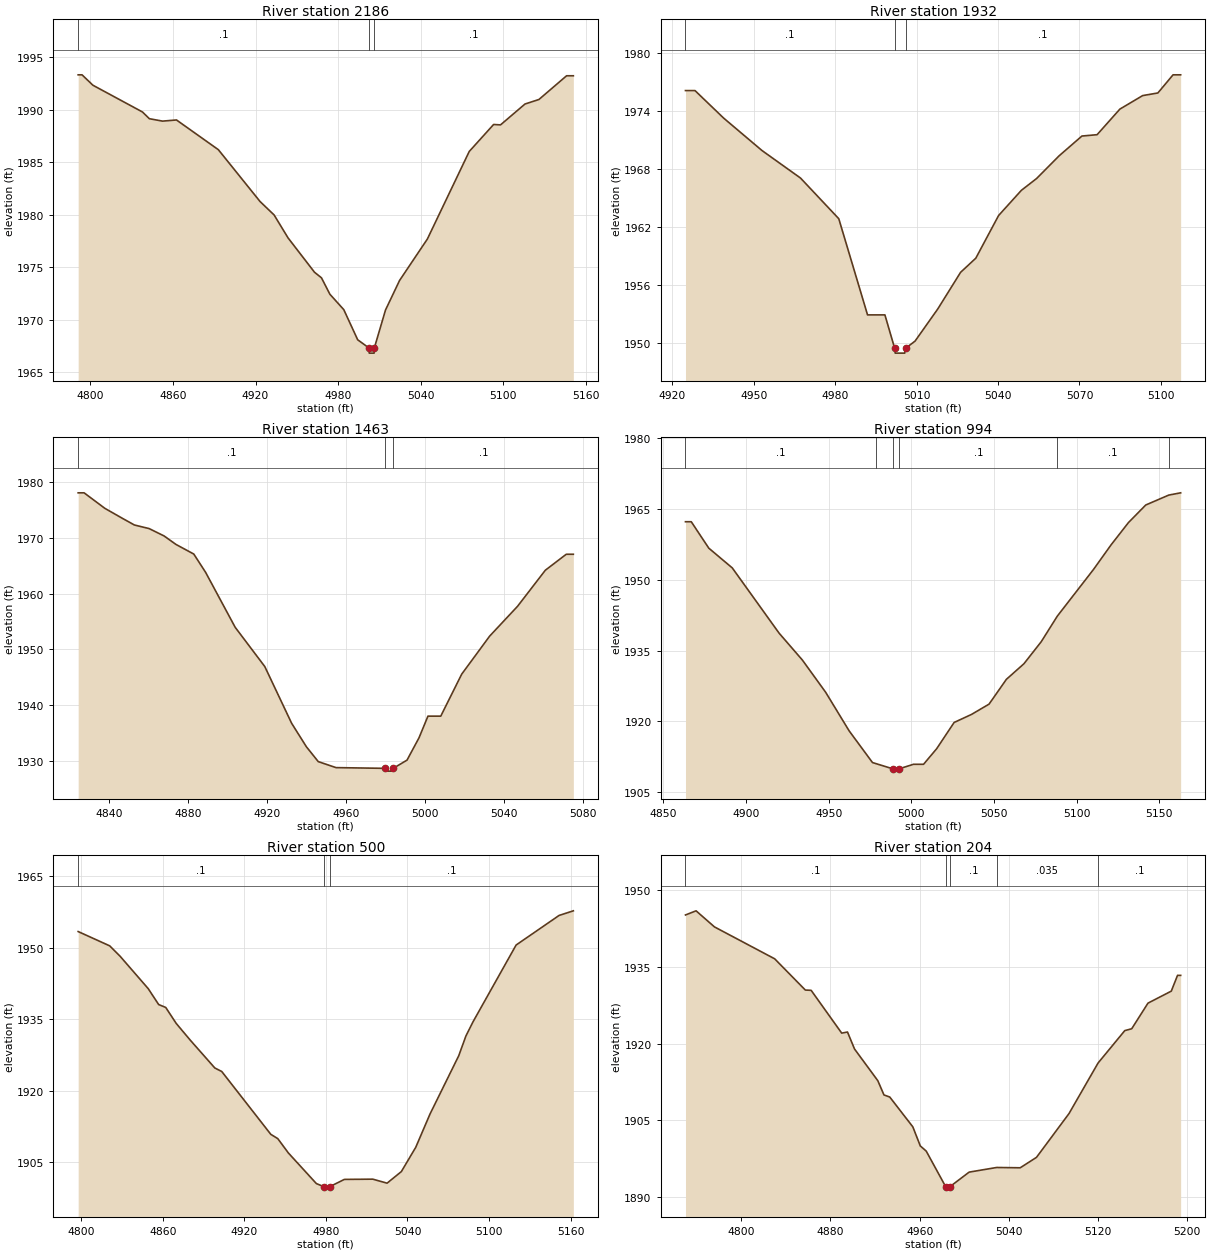
Type RM Length L Ch R = 1 ,2186    ,254,254,254
BEGIN DESCRIPTION:
Stream0215 5.0
END DESCRIPTION:
XS GIS Cut Line= 2
      1859164.48     13946842.64      1859519.69     13946898.64
#Sta/Elev= 30
  4791.2 1993.31    4794 1993.31  4801.9 1992.32  4837.9 1989.77  4842.9 1989.13
  4852.5  1988.9  4862.6 1989.01    4893 1986.18  4923.3 1981.24  4933.5 1979.96
  4943.6 1977.78  4962.8 1974.51  4967.9 1973.97    4974 1972.41  4984.1 1970.94
  4994.2 1968.07  5002.3  1967.3  5002.6  1966.8  5006.1  1966.8  5006.3  1967.3
  5014.4 1970.91  5024.6 1973.72  5044.8 1977.67  5075.2 1986.01  5092.9 1988.58
  5097.9 1988.54  5115.7 1990.53  5125.8 1990.96  5145.9 1993.22  5150.8 1993.22
#Mann= 3 ,-1 , 0
  4791.2      .1       0  5002.3     .05       0  5006.3      .1       0
Bank Sta=5002.3,5006.3
XS Rating Curve= 0 ,0
Exp/Cntr=0.3,0.1

Type RM Length L Ch R = 1 ,1932    ,469,469,469
BEGIN DESCRIPTION:
Stream0215 4.0
END DESCRIPTION:
XS GIS Cut Line= 3
      1859175.03     13947025.03        1859225.       13947075.
      1859325.03     13947125.01
#Sta/Elev= 28
  4924.8 1976.15  4928.3 1976.15  4938.9 1973.29    4953 1969.94  4967.2 1967.09
  4981.3 1962.88  4991.9 1952.92  4995.5 1952.92  4998.3 1952.92  5001.9 1949.46
  5002.1 1948.96  5005.6 1948.96  5005.9 1949.46  5009.4  1950.2  5017.8 1953.54
  5026.2 1957.33  5031.8 1958.79  5040.2 1963.21  5048.6 1965.82  5054.2 1967.04
  5062.5 1969.39  5070.9 1971.44  5076.5 1971.58  5084.9 1974.23  5093.3 1975.63
  5098.9  1975.9  5104.5 1977.78  5107.3 1977.78
#Mann= 3 ,-1 , 0
  4924.8      .1       0  5001.9     .05       0  5005.9      .1       0
Bank Sta=5001.9,5005.9
XS Rating Curve= 0 ,0
Exp/Cntr=0.3,0.1

Type RM Length L Ch R = 1 ,1463    ,469,469,469
BEGIN DESCRIPTION:
Stream0215 3.0
END DESCRIPTION:
XS GIS Cut Line= 3
      1858875.01     13947275.01        1858975.       13947425.
      1859025.02     13947475.02
#Sta/Elev= 30
  4824.2 1978.14  4827.2 1978.14  4837.7 1975.36  4846.7 1973.54  4852.7 1972.36
  4860.2 1971.71  4867.8 1970.38  4873.8 1968.86  4882.8 1967.14  4888.8 1963.85
  4903.8 1953.97  4918.8 1946.92  4932.4 1936.73  4939.9  1932.5  4945.9 1929.84
  4954.9 1928.76  4979.9 1928.63  4980.2 1928.13  4983.7 1928.13  4983.9 1928.63
  4990.9 1930.11    4997 1934.14  5001.5 1938.01    5008 1938.01  5018.6 1945.55
  5032.8  1952.4  5046.9 1957.74    5061 1964.23  5071.6  1967.1  5075.2  1967.1
#Mann= 3 ,-1 , 0
  4824.2      .1       0  4979.9     .05       0  4983.9      .1       0
Bank Sta=4979.9,4983.9
XS Rating Curve= 0 ,0
Exp/Cntr=0.3,0.1

Type RM Length L Ch R = 1 ,994     ,494,494,494
BEGIN DESCRIPTION:
Stream0215 2.0
END DESCRIPTION:
XS GIS Cut Line= 3
      1858625.01     13947675.01        1858725.       13947775.
      1858874.98     13947824.99
#Sta/Elev= 30
  4863.4 1962.33  4866.9 1962.33  4877.5 1956.73  4891.7 1952.54    4920 1938.72
  4934.1 1933.01  4948.2 1926.17  4962.4 1917.99  4976.5 1911.28  4978.7 1911.04
  4988.7 1909.96  4988.9 1909.46  4992.4 1909.46  4992.7 1909.96  5001.3 1910.91
  5007.4 1910.91  5015.3  1914.2  5025.9 1919.78  5036.4 1921.48    5047 1923.66
  5057.5 1928.92  5068.1 1932.22  5078.6 1936.91  5088.3 1942.32  5110.2 1952.22
  5120.8 1957.42  5131.3 1962.14  5141.8 1965.88  5155.7 1967.98  5162.9 1968.46
#Mann= 6 ,-1 , 0
  4863.4      .1       0  4978.7      .1       0  4988.7     .05       0
  4992.7      .1       0  5088.3      .1       0  5155.7     .07       0
Bank Sta=4988.7,4992.7
XS Rating Curve= 0 ,0
Exp/Cntr=0.3,0.1

Type RM Length L Ch R = 1 ,500     ,296,296,296
BEGIN DESCRIPTION:
Stream0215 1.0
END DESCRIPTION:
XS GIS Cut Line= 3
      1858325.01     13947925.04        1858375.       13948125.
      1858424.99     13948274.97
#Sta/Elev= 30
  4797.8 1953.37    4821 1950.37  4828.7 1948.17  4849.3  1941.4    4857 1938.06
  4862.2 1937.45  4869.9  1934.1  4880.2  1930.6  4898.3 1924.75  4903.4 1924.01
  4939.5 1910.82  4944.6 1909.93  4952.4 1906.92    4973 1900.49  4978.7 1899.83
    4979 1899.33  4982.5 1899.33  4982.7 1899.83  4993.6 1901.37  5014.5 1901.42
    5025 1900.58  5035.5 1903.01  5046.1 1908.11  5056.6  1915.1  5077.7 1927.31
    5083 1931.47  5088.2 1934.43  5119.9 1950.54  5151.5 1956.75    5162 1957.72
#Mann= 3 ,-1 , 0
  4797.8      .1       0  4978.7     .05       0  4982.7      .1       0
Bank Sta=4978.7,4982.7
XS Rating Curve= 0 ,0
Exp/Cntr=0.3,0.1

Type RM Length L Ch R = 1 ,204     ,114,114,114
BEGIN DESCRIPTION:
Stream0215 0.0
END DESCRIPTION:
XS GIS Cut Line= 3
      1858027.42     13947960.19      1858102.47      13948203.3
      1858254.45     13948316.76
#Sta/Elev= 30
    4750 1945.19  4759.5    1946    4776 1942.85    4830  1936.6  4857.5 1930.48
  4862.7 1930.43  4890.1 1922.05  4895.3 1922.26  4901.6 1918.94  4922.5 1912.73
    4928 1909.94  4933.2 1909.53  4953.9 1903.69  4960.6 1899.95  4965.9 1898.94
  4983.3 1891.99  4983.5 1891.49  4987.3 1891.99  5004.4 1894.82  5029.1 1895.73
  5050.2 1895.67  5064.8 1897.71    5094  1906.3    5120 1916.18    5144 1922.54
  5150.2  1922.9  5164.8 1927.92  5185.7 1930.27  5191.3 1933.36  5194.1 1933.36
#Mann= 5 ,-1 , 0
    4750      .1       0  4983.3     .05       0  4987.3      .1       0
  5029.1    .035       0    5120      .1       0
Bank Sta=4983.3,4987.3
XS Rating Curve= 0 ,0
Exp/Cntr=0.3,0.1

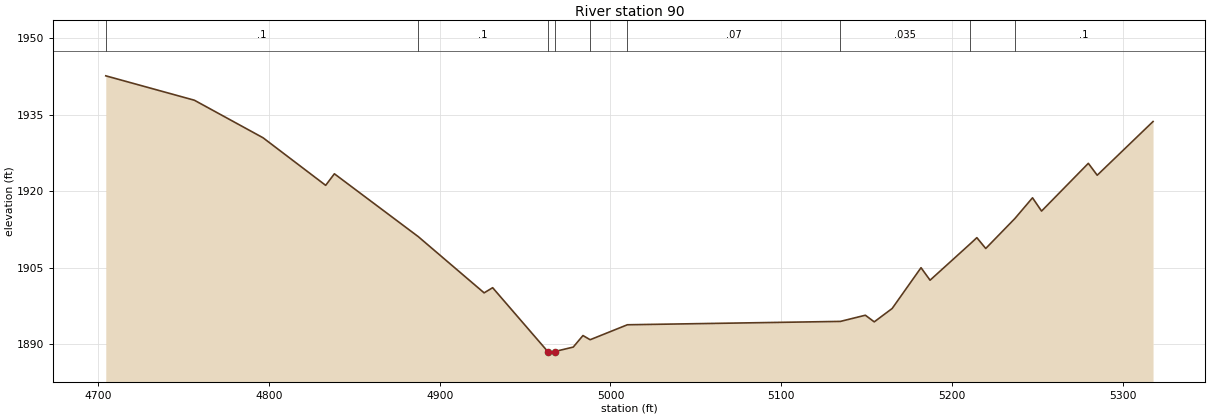
Type RM Length L Ch R = 1 ,90      ,0,0,0
BEGIN DESCRIPTION:
Stream0215 0.1
END DESCRIPTION:
XS GIS Cut Line= 4
      1857956.27     13947933.36      1857984.05     13948195.56
      1858013.56     13948270.21      1858271.03      13948349.7
#Sta/Elev= 30
  4704.4  1942.6  4756.3 1937.82  4796.5 1930.47  4833.2 1921.15  4838.3 1923.41
  4887.4 1911.11    4926 1900.09    4931  1901.1  4963.3 1888.59  4963.5 1888.09
  4967.3 1888.59  4978.2 1889.47  4983.9 1891.73  4988.1 1890.91  5009.9 1893.84
  5134.7  1894.5  5149.3 1895.71  5154.5 1894.41    5165 1897.03  5181.9 1905.02
  5187.2 1902.57  5210.8 1909.72  5214.6  1910.9  5219.8 1908.78  5236.9 1914.66
  5247.2 1918.71  5252.5 1916.11  5279.9 1925.46  5285.1 1923.13  5317.8 1933.65
#Mann= 9 ,-1 , 0
  4704.4      .1       0  4887.4      .1       0  4963.3     .05       0
  4967.3      .1       0  4988.1    .035       0  5009.9     .07       0
  5134.7    .035       0  5210.8     .07       0  5236.9      .1       0
Bank Sta=4963.3,4967.3
XS Rating Curve= 0 ,0
Exp/Cntr=0.3,0.1

Chan Stop Cuts=-1
Use User Specified Reach Order=0
Composite Channel Slope=5