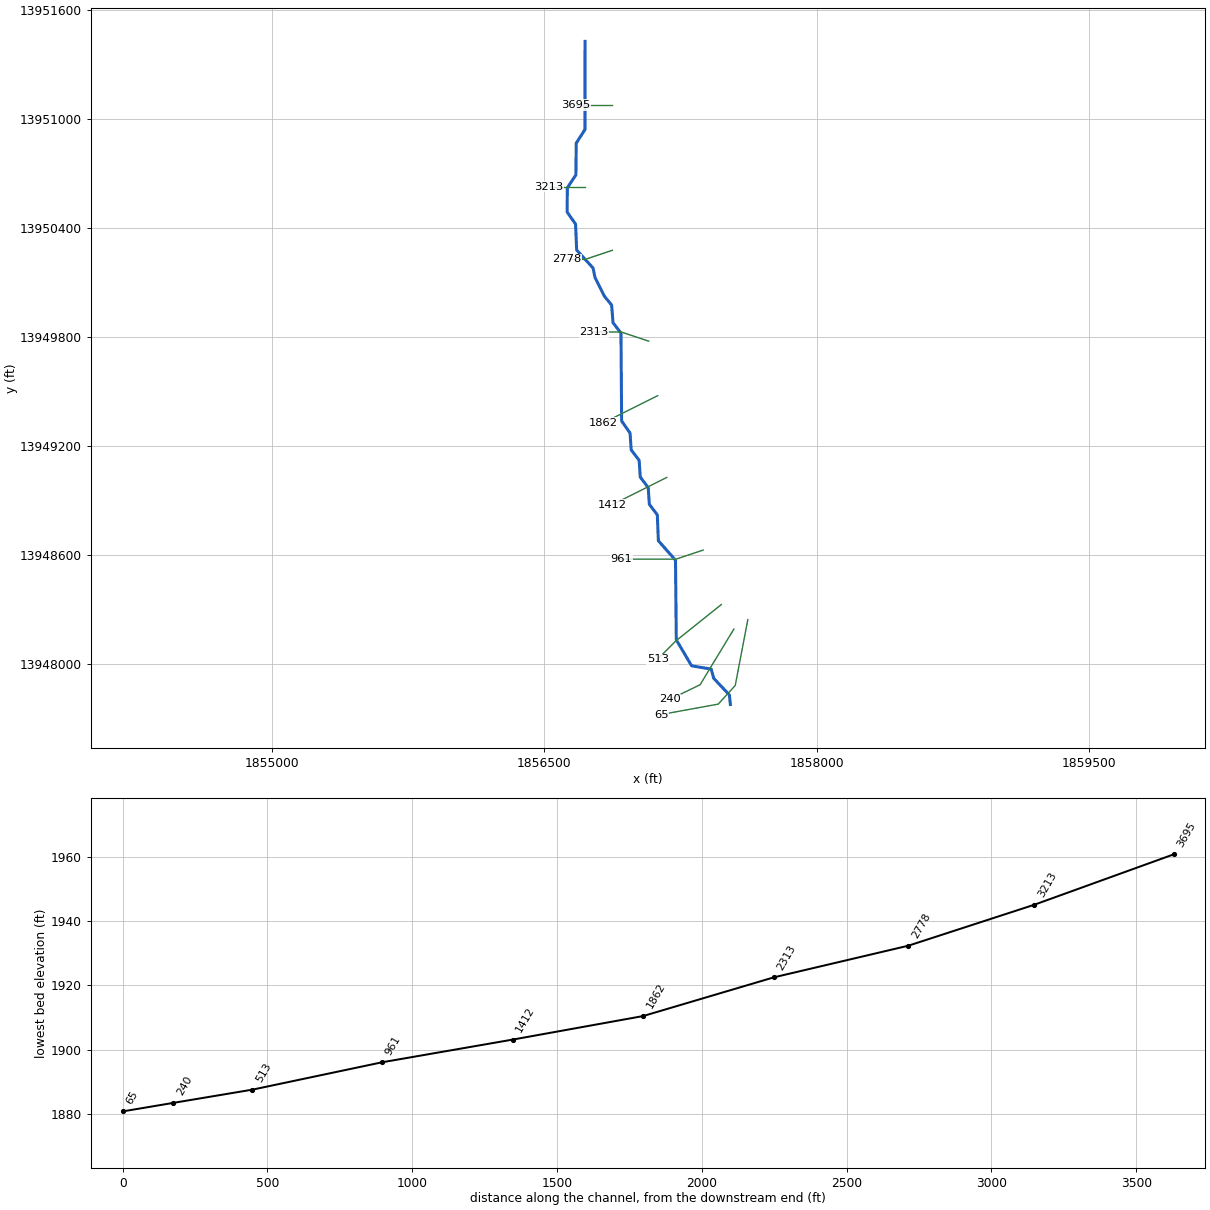
--- Stream0216.prj (project) ---

Proj Title=Stream0216 Base Level Engineering
Current Plan=p01
Default Exp/Contr=0.3,0.1
English Units
Geom File=g01
Flow File=f01
Plan File=p01
Y Axis Title=Elevation
X Axis Title(PF)=Main Channel Distance
X Axis Title(XS)=Station
BEGIN DESCRIPTION:
Stream0216
END DESCRIPTION:
DSS Export Rating Curves= 0
DSS Export Rating Curve Sorted= 0
DSS Export Volume Flow Curves= 0
DXF OffsetX= 0
DXF OffsetY= 0
DXF ScaleX= 1
DXF ScaleY= 10

--- Stream0216.p01 (plan) ---

Plan Title=Multiple Run
Short Identifier=Multiple
Geom File=g01
Flow File=f01
Subcritical Flow
K Sum by GR= 0
Std Step Tol= 0.01
Critical Tol= 0.01
Num of Std Step Trials= 20
Max Error Tol= 0.3
Flow Tol Ratio= 0.001
Split Flow NTrial= 30
Split Flow Tol= 0.02
Split Flow Ratio= 0.02
Log Output Level= 0
Friction Slope Method= 1
Unsteady Friction Slope Method= 2
Unsteady Bridges Friction Slope Method= 1
Parabolic Critical Depth
Global Vel Dist=  1 , 1 , 1
Global Log Level= 0
CheckData=True
Encroach Param= -1, 0, 0, 0
BEGIN DESCRIPTION:
Multiple Run
END DESCRIPTION:

--- Stream0216.f01 (steady flow) ---

Flow Title=Multiple
Program Version=4.10
Number of Profiles= 7
Profile Names=10-year,25-year,50-year,1pct_min,100-year,1pct_plu,500-year
River Rch & RM=Stream0216,Reach-1         ,3695
     969    1652    2303    1554    3101    6188    5551
Boundary for River Rch & Prof#=Stream0216,Reach-1         , 1
Up Type= 0
Dn Type= 3
Dn Slope=0.01
Boundary for River Rch & Prof#=Stream0216,Reach-1         , 2
Up Type= 0
Dn Type= 3
Dn Slope=0.01
Boundary for River Rch & Prof#=Stream0216,Reach-1         , 3
Up Type= 0
Dn Type= 3
Dn Slope=0.01
Boundary for River Rch & Prof#=Stream0216,Reach-1         , 4
Up Type= 0
Dn Type= 3
Dn Slope=0.01
Boundary for River Rch & Prof#=Stream0216,Reach-1         , 5
Up Type= 0
Dn Type= 3
Dn Slope=0.01
Boundary for River Rch & Prof#=Stream0216,Reach-1         , 6
Up Type= 0
Dn Type= 3
Dn Slope=0.01
Boundary for River Rch & Prof#=Stream0216,Reach-1         , 7
Up Type= 0
Dn Type= 3
Dn Slope=0.01
DSS Import GetInterval= 0
DSS Import GetPeak= 0
DSS Import FillOption= 0

--- Stream0216.g01 (geometry) ---

Geom Title=Existing Conditions
Program Version=4.10

River Reach=Stream0216      ,Reach-1
Reach XY= 30
        1856725.       13951425.      1856724.48     13950940.22
      1856676.22     13950864.49      1856674.48     13950690.22
      1856627.25     13950619.06      1856626.21     13950485.51
      1856672.73     13950419.06      1856678.55     13950276.47
      1856769.15     13950177.29      1856779.19     13950126.74
      1856831.12     13950022.82      1856871.17     13949973.42
      1856878.86      13949876.6      1856922.74     13949819.06
      1856926.22      13949335.5      1856972.64     13949269.02
      1856978.85      13949176.6      1857022.65     13949119.03
      1857028.85      13949026.6      1857072.65     13948969.03
      1857078.86      13948876.6      1857122.73     13948819.06
      1857128.56     13948676.47      1857222.93     13948569.14
      1857227.24     13948130.93      1857311.37     13947988.27
      1857419.53     13947969.74      1857433.31      13947919.3
      1857519.67     13947827.51        1857525.       13947775.

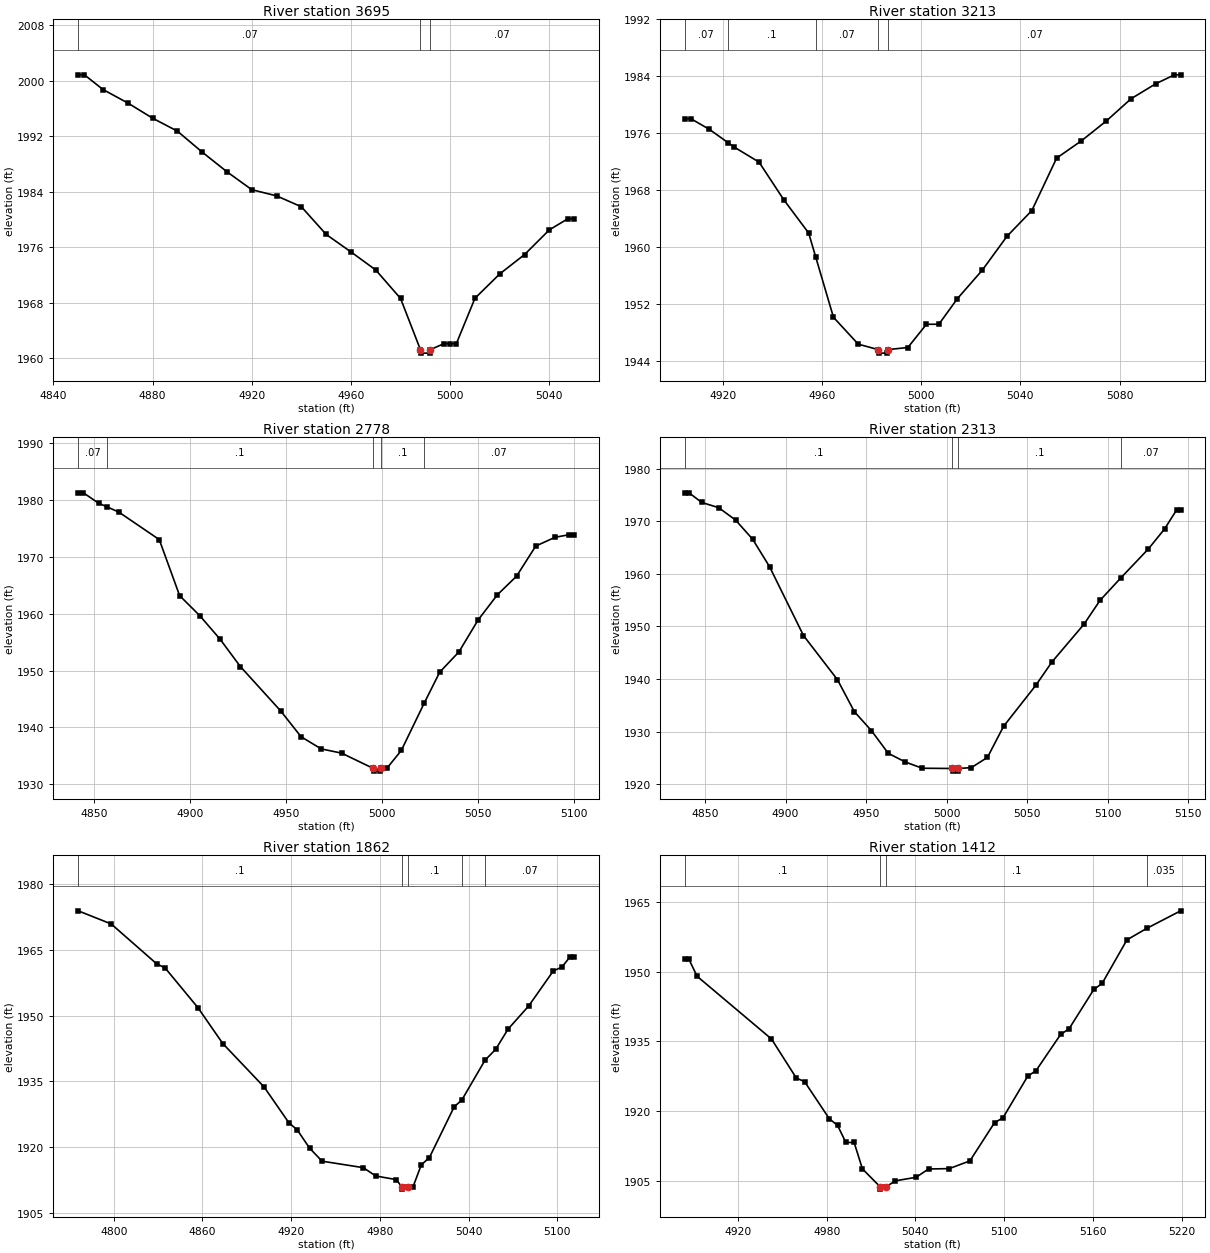
Type RM Length L Ch R = 1 ,3695    ,482,482,482
BEGIN DESCRIPTION:
Stream0216 8.0
END DESCRIPTION:
XS GIS Cut Line= 3
      1856875.02       13951075.        1856725.       13951075.
      1856675.02       13951075.
#Sta/Elev= 28
    4850 2000.85  4852.5 2000.85    4860 1998.73    4870 1996.79    4880  1994.6
    4890 1992.73    4900 1989.71    4910 1986.87    4920 1984.29    4930  1983.4
    4940 1981.83    4950 1977.84    4960 1975.32    4970 1972.71    4980 1968.61
    4988 1961.23  4988.3 1960.73  4991.8 1960.73    4992 1961.23  4997.5  1962.1
    5000  1962.1  5002.5  1962.1    5010 1968.64    5020 1972.15    5030 1974.94
    5040  1978.5  5047.5 1980.11    5050 1980.11
#Mann= 3 ,-1 , 0
    4850     .07       0    4988     .05       0    4992     .07       0
Bank Sta=4988,4992
XS Rating Curve= 0 ,0
Exp/Cntr=0.3,0.1

Type RM Length L Ch R = 1 ,3213    ,435,435,435
BEGIN DESCRIPTION:
Stream0216 7.0
END DESCRIPTION:
XS GIS Cut Line= 3
      1856724.96       13950625.        1856625.       13950625.
      1856524.96       13950625.
#Sta/Elev= 29
  4904.6 1978.02  4907.1 1978.02  4914.6 1976.51    4922 1974.67  4924.6 1974.02
  4934.6 1971.91  4944.6  1966.6  4954.6 1961.94  4957.5  1958.5  4964.6 1950.09
  4974.6 1946.31  4982.6 1945.55  4982.8 1945.05  4986.3 1945.05  4986.6 1945.55
  4994.6 1945.84  5002.1 1949.11  5007.1 1949.11  5014.6 1952.72  5024.6 1956.71
  5034.6 1961.49  5044.6  1965.1  5054.6 1972.48  5064.6 1974.91  5074.6 1977.69
  5084.6 1980.82  5094.6 1982.94  5102.1 1984.19  5104.6 1984.19
#Mann= 5 ,-1 , 0
  4904.6     .07       0    4922      .1       0  4957.5     .07       0
  4982.6     .05       0  4986.6     .07       0
Bank Sta=4982.6,4986.6
XS Rating Curve= 0 ,0
Exp/Cntr=0.3,0.1

Type RM Length L Ch R = 1 ,2778    ,465,465,465
BEGIN DESCRIPTION:
Stream0216 6.0
END DESCRIPTION:
XS GIS Cut Line= 3
      1856875.04     13950275.01        1856725.       13950225.
      1856624.96       13950225.
#Sta/Elev= 30
  4841.8 1981.29  4844.5 1981.29  4852.4 1979.47    4857 1978.79  4862.9 1977.91
    4884 1973.06  4894.6  1963.2  4905.1 1959.67  4915.6 1955.56  4926.2 1950.73
  4947.3 1942.88  4957.8 1938.38  4968.3 1936.23  4978.9 1935.49  4995.3 1932.82
  4995.6 1932.32  4999.1 1932.32  4999.3 1932.82  5002.5 1932.82    5010 1935.95
  5021.9 1944.26    5030 1949.73    5040  1953.3    5050 1958.92    5060 1963.34
    5070 1966.62    5080 1971.92    5090 1973.46  5097.5 1973.93    5100 1973.93
#Mann= 5 ,-1 , 0
  4841.8     .07       0    4857      .1       0  4995.3     .05       0
  4999.3      .1       0  5021.9     .07       0
Bank Sta=4995.3,4999.3
XS Rating Curve= 0 ,0
Exp/Cntr=0.3,0.1

Type RM Length L Ch R = 1 ,2313    ,451,451,451
BEGIN DESCRIPTION:
Stream0216 5.0
END DESCRIPTION:
XS GIS Cut Line= 3
      1857075.02     13949774.99        1856925.       13949825.
      1856775.03       13949825.
#Sta/Elev= 30
  4837.3 1975.38    4840 1975.38  4847.9 1973.55  4858.4 1972.56  4868.9 1970.21
  4879.5 1966.57    4890 1961.35  4911.1 1948.25  4932.2 1939.86  4942.7 1933.78
  4953.3 1930.17  4963.8 1925.85  4974.4  1924.2  4984.9 1923.02  5003.4 1922.97
  5003.7 1922.47  5007.2 1922.47  5007.4 1922.97  5015.4 1923.14  5025.4 1925.08
  5035.4 1930.98  5055.4 1938.77  5065.4  1943.2  5085.4 1950.41  5095.4 1954.96
  5108.3 1959.22  5125.4 1964.72  5135.4  1968.5  5142.9 1972.12  5145.4 1972.12
#Mann= 4 ,-1 , 0
  4837.3      .1       0  5003.4     .05       0  5007.4      .1       0
  5108.3     .07       0
Bank Sta=5003.4,5007.4
XS Rating Curve= 0 ,0
Exp/Cntr=0.3,0.1

Type RM Length L Ch R = 1 ,1862    ,450,450,450
BEGIN DESCRIPTION:
Stream0216 4.0
END DESCRIPTION:
XS GIS Cut Line= 3
      1857124.97     13949474.98        1856925.       13949375.
      1856824.98     13949324.99
#Sta/Elev= 30
    4776 1973.86  4798.3 1970.87  4829.1 1961.77  4834.7 1960.87    4857 1951.78
  4873.8 1943.61  4901.7 1933.73  4918.5 1925.56  4924.1 1923.96  4932.5 1919.78
  4940.9 1916.82  4968.8 1915.34  4977.2 1913.45  4991.2 1912.61  4994.8 1910.95
    4995 1910.45  4998.8 1910.95  5002.4 1910.95    5008 1915.97  5013.5 1917.64
  5030.3 1929.23  5035.4 1930.73  5051.1 1939.82  5058.3 1942.29  5066.7 1946.91
  5080.6 1952.16  5097.4 1960.21    5103    1961  5108.6 1963.36  5111.4 1963.36
#Mann= 5 ,-1 , 0
    4776      .1       0  4994.8     .05       0  4998.8      .1       0
  5035.4      .1       0  5051.1     .07       0
Bank Sta=4994.8,4998.8
XS Rating Curve= 0 ,0
Exp/Cntr=0.3,0.1

Type RM Length L Ch R = 1 ,1412    ,451,451,451
BEGIN DESCRIPTION:
Stream0216 3.0
END DESCRIPTION:
XS GIS Cut Line= 3
        1857175.       13949025.        1857075.       13948975.
      1856875.01       13948875.
#Sta/Elev= 30
    4884 1952.74  4886.8 1952.74  4892.4 1949.03  4942.7 1935.51  4959.5 1927.09
  4965.1 1926.31  4981.8 1918.32  4987.4 1916.87    4993  1913.2  4998.6  1913.2
  5004.2 1907.51  5016.2 1903.64  5016.4 1903.14  5020.2 1903.64  5026.5 1904.93
  5040.5 1905.69  5048.9 1907.48  5062.9 1907.56  5076.9 1909.23  5093.6 1917.49
  5099.2 1918.49    5116 1927.49  5121.6 1928.68  5138.3 1936.51  5143.9 1937.68
  5160.7 1946.19  5166.3 1947.48  5183.1 1956.88  5196.4 1959.34  5219.4 1963.14
#Mann= 4 ,-1 , 0
    4884      .1       0  5016.2     .05       0  5020.2      .1       0
  5196.4    .035       0
Bank Sta=5016.2,5020.2
XS Rating Curve= 0 ,0
Exp/Cntr=0.3,0.1

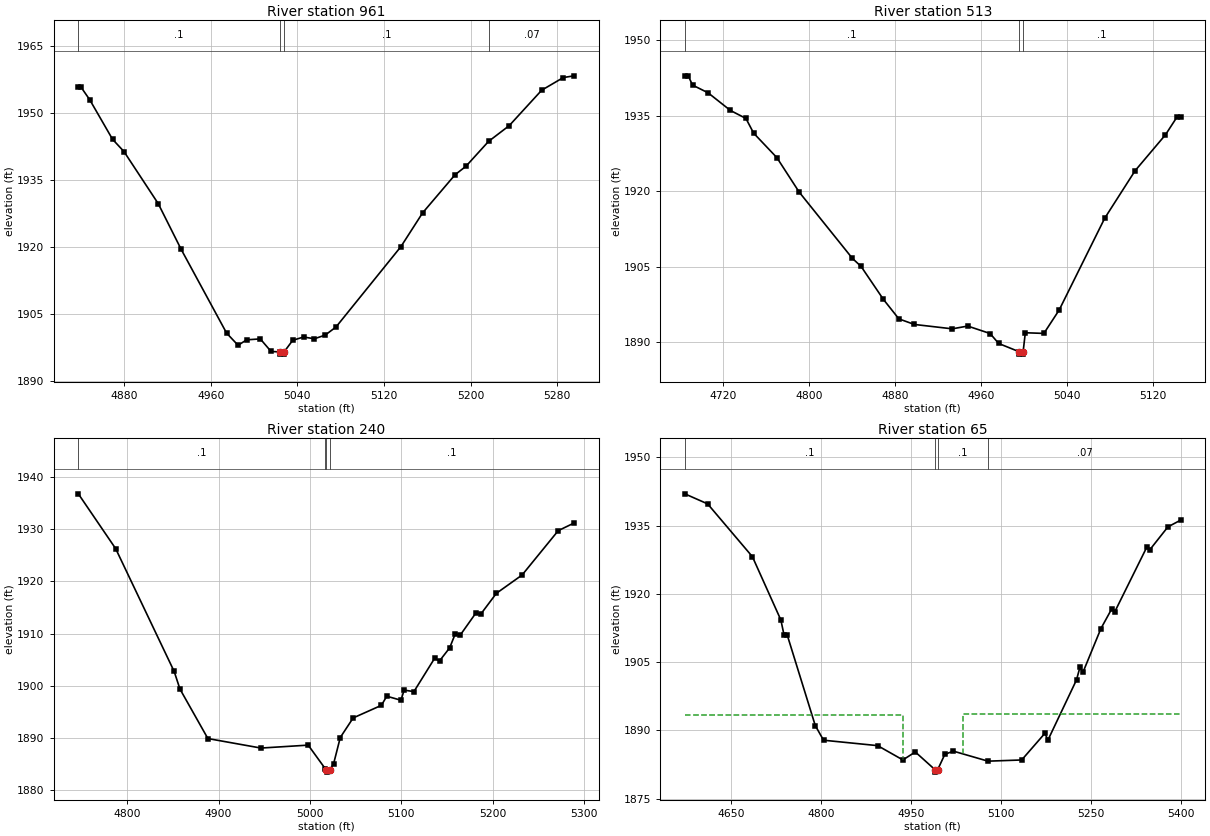
Type RM Length L Ch R = 1 ,961     ,448,448,448
BEGIN DESCRIPTION:
Stream0216 2.0
END DESCRIPTION:
XS GIS Cut Line= 3
      1857375.01       13948625.        1857225.       13948575.
      1856925.03       13948575.
#Sta/Elev= 30
  4837.6 1955.77  4840.3 1955.77  4848.2    1953  4869.2 1944.18  4879.8 1941.42
  4911.4 1929.78  4932.5 1919.59  4974.6 1900.79  4985.2 1898.07  4993.1 1899.29
  5005.7  1899.5  5015.7 1896.68  5023.7 1896.59    5024 1896.09  5027.5 1896.09
  5027.7 1896.59  5035.7 1899.19  5045.7 1899.92  5055.7 1899.53  5065.7 1900.35
  5075.7 1902.17  5135.7 1920.17  5155.7 1927.71  5185.7 1936.25  5195.7 1938.13
  5216.6  1943.7  5235.7 1947.23  5265.7 1955.16  5285.7    1958  5295.7 1958.38
#Mann= 4 ,-1 , 0
  4837.6      .1       0  5023.7     .05       0  5027.7      .1       0
  5216.6     .07       0
Bank Sta=5023.7,5027.7
XS Rating Curve= 0 ,0
Exp/Cntr=0.3,0.1

Type RM Length L Ch R = 1 ,513     ,273,273,273
BEGIN DESCRIPTION:
Stream0216 1.0
END DESCRIPTION:
XS GIS Cut Line= 3
      1857475.03     13948325.03        1857225.       13948125.
      1857125.01     13948025.01
#Sta/Elev= 30
  4684.1 1942.91  4687.3 1942.91  4691.3 1941.07  4705.8 1939.53  4726.6 1936.02
    4741 1934.44  4748.2 1931.51  4769.8 1926.65  4790.6 1919.79  4840.2  1906.6
  4848.2 1905.02    4869 1898.46  4883.4 1894.59  4897.8 1893.48  4933.1 1892.61
  4947.5 1893.16  4968.3 1891.68  4976.3  1889.7  4995.1 1888.08  4995.3 1887.58
  4998.8 1887.58  4999.1 1888.08  5001.1 1891.83  5018.4  1891.7  5032.6 1896.34
    5075 1914.59  5103.3 1924.04  5131.6 1931.19  5142.2 1934.68  5145.7 1934.68
#Mann= 3 ,-1 , 0
  4684.1      .1       0  4995.1     .05       0  4999.1      .1       0
Bank Sta=4995.1,4999.1
XS Rating Curve= 0 ,0
Exp/Cntr=0.3,0.1

Type RM Length L Ch R = 1 ,240     ,175,175,175
BEGIN DESCRIPTION:
Stream0216 0.0
END DESCRIPTION:
XS GIS Cut Line= 3
      1857544.21     13948190.09      1857358.47     13947883.92
      1857192.41      13947803.3
#Sta/Elev= 30
  4746.5 1936.77  4787.4 1926.26  4851.4 1902.75  4857.7 1899.39  4888.3  1889.9
  4946.4 1888.08  4998.1 1888.64  5016.8 1884.12  5018.1 1883.97  5018.3 1883.47
  5022.1 1883.97  5025.9 1885.07  5033.2  1890.1  5047.3 1893.85  5078.2 1896.26
  5084.1 1898.01  5099.6 1897.24  5103.1 1899.18  5113.8 1898.89  5136.4 1905.25
  5141.9 1904.79  5152.9 1907.26  5158.9 1909.88  5164.5 1909.71  5181.5 1913.91
    5187 1913.73  5204.1 1917.72  5232.2 1921.22  5271.8 1929.72  5289.2 1931.19
#Mann= 4 ,-1 , 0
  4746.5      .1       0  5016.8      .1       0  5018.1     .05       0
  5022.1      .1       0
Bank Sta=5018.1,5022.1
XS Rating Curve= 0 ,0
Exp/Cntr=0.3,0.1

Type RM Length L Ch R = 1 ,65      ,0,0,0
BEGIN DESCRIPTION:
Stream0216 0.1
END DESCRIPTION:
XS GIS Cut Line= 4
      1857621.19     13948242.41      1857551.76     13947879.59
      1857458.01     13947777.16      1857144.14     13947719.93
#Sta/Elev= 30
  4572.7 1941.96  4610.8 1939.75  4685.5 1928.15    4733 1914.24  4738.4 1910.87
  4743.4 1911.03  4790.4 1891.05  4804.2 1887.83  4894.5 1886.64  4936.6  1883.5
  4957.3 1885.25  4990.5 1881.32  4990.7 1880.82  4994.5 1881.32  5006.6 1884.73
  5020.8 1885.43  5078.6 1883.23  5134.8 1883.49  5173.5 1889.34  5178.6 1887.86
  5226.3 1901.09  5231.9 1903.82    5237 1902.74    5267 1912.36  5285.2 1916.72
  5290.3 1916.09  5343.5 1930.23  5348.6 1929.67  5378.8  1934.7    5400 1936.18
#Mann= 4 ,-1 , 0
  4572.7      .1       0  4990.5     .05       0  4994.5      .1       0
  5078.6     .07       0
#XS Ineff= 2 , 0
         4937.47 1893.34 5036.13         1893.68
Permanent Ineff=
       F       F
Bank Sta=4990.5,4994.5
XS Rating Curve= 0 ,0
Exp/Cntr=0.3,0.1

Chan Stop Cuts=-1
Use User Specified Reach Order=0
Composite Channel Slope=5