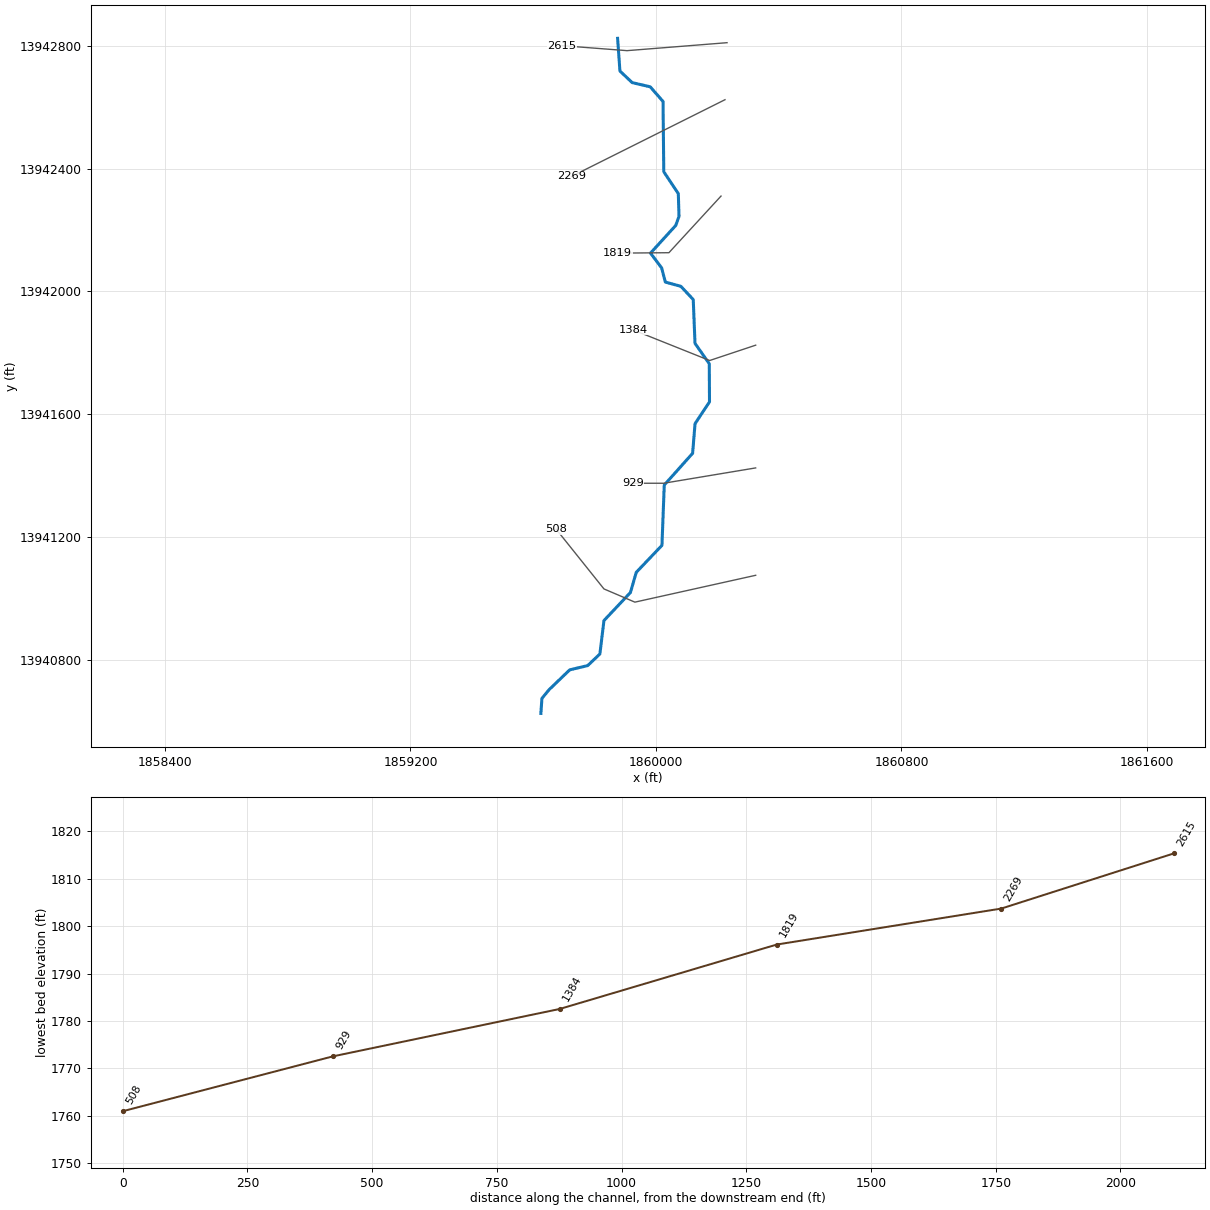
--- Stream0217.prj (project) ---

Proj Title=Stream0217 Base Level Engineering
Current Plan=p01
Default Exp/Contr=0.3,0.1
English Units
Geom File=g01
Flow File=f01
Plan File=p01
BEGIN DESCRIPTION:
Stream0217
END DESCRIPTION:

--- Stream0217.p01 (plan) ---

Plan Title=Multiple Run
Short Identifier=Multiple
Geom File=g01
Flow File=f01
Subcritical Flow
K Sum by GR= 0
Std Step Tol= 0.01
Critical Tol= 0.01
Num of Std Step Trials= 20
Max Error Tol= 0.3
Flow Tol Ratio= 0.001
Split Flow NTrial= 30
Split Flow Tol= 0.02
Split Flow Ratio= 0.02
Log Output Level= 0
Friction Slope Method= 1
Unsteady Friction Slope Method= 2
Unsteady Bridges Friction Slope Method= 1
Parabolic Critical Depth
Global Vel Dist=  1 , 1 , 1
Global Log Level= 0
CheckData=True
Encroach Param= -1, 0, 0, 0
BEGIN DESCRIPTION:
Multiple Run
END DESCRIPTION:

--- Stream0217.f01 (steady flow) ---

Flow Title=Multiple
Number of Profiles=7
Profile Names=10-year,25-year,50-year,1pct_min,100-year,1pct_plu,500-year
River Rch & RM= Stream0217,Reach-1,2615
     608    1007    1378     915    1826    3643    3157
Boundary for River Rch & Prof#=Stream0217,Reach-1,1
Up Type=0
Dn Type=3
Dn Slope=0.005
Boundary for River Rch & Prof#=Stream0217,Reach-1,2
Up Type=0
Dn Type=3
Dn Slope=0.005
Boundary for River Rch & Prof#=Stream0217,Reach-1,3
Up Type=0
Dn Type=3
Dn Slope=0.005
Boundary for River Rch & Prof#=Stream0217,Reach-1,4
Up Type=0
Dn Type=3
Dn Slope=0.005
Boundary for River Rch & Prof#=Stream0217,Reach-1,5
Up Type=0
Dn Type=3
Dn Slope=0.005
Boundary for River Rch & Prof#=Stream0217,Reach-1,6
Up Type=0
Dn Type=3
Dn Slope=0.005
Boundary for River Rch & Prof#=Stream0217,Reach-1,7
Up Type=0
Dn Type=3
Dn Slope=0.005

--- Stream0217.g01 (geometry) ---

Geom Title=Existing Conditions

River Reach=Stream0217,Reach-1
Reach XY= 30
      1859875.00     13942825.00      1859882.60     13942718.46
      1859922.46     13942680.74      1859981.36     13942666.97
      1860023.02     13942619.33      1860025.52     13942390.22
      1860072.84     13942319.02      1860075.20     13942245.05
      1860064.52     13942215.21      1859982.28     13942125.05
      1860018.44     13942076.96      1860030.59     13942030.64
      1860081.08     13942016.85      1860121.52     13941973.73
      1860127.27     13941830.94      1860173.79     13941764.49
      1860174.50     13941640.22      1860127.36     13941569.02
      1860119.46     13941472.58      1860027.07     13941369.14
      1860019.53     13941172.55      1859935.80     13941084.67
      1859916.82     13941018.96      1859830.54     13940927.42
      1859817.25     13940818.55      1859777.57     13940780.74
      1859718.96     13940766.85      1859651.32     13940701.87
      1859628.27     13940673.66      1859625.00     13940625.00

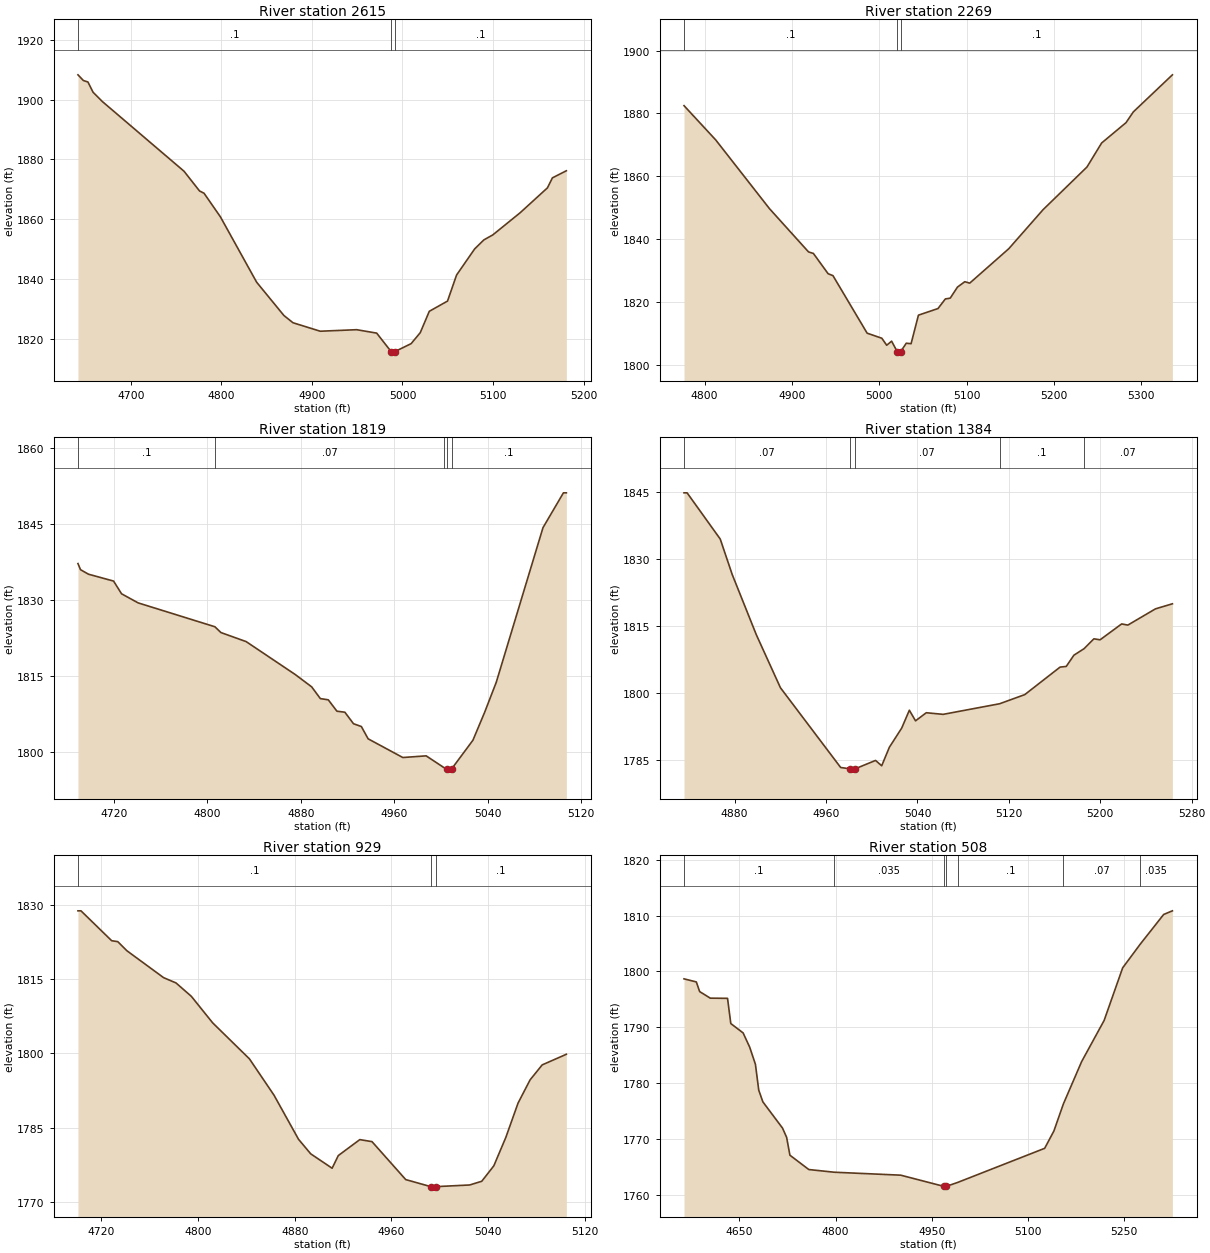
Type RM Length L Ch R = 1,2615,346,346,346
BEGIN DESCRIPTION:
Stream0217 6.0
END DESCRIPTION:
XS GIS Cut Line= 3
      1860231.69     13942810.81      1859905.79     13942784.87
      1859694.15     13942801.13
#Sta/Elev= 30
  4641.7 1908.25  4647.7 1906.35  4652.7 1905.86  4658.4 1902.43  4668.5 1899.37
  4758.8 1876.08  4775.9 1869.50  4780.9 1868.73  4798.9 1860.89  4839.0 1839.03
  4869.1 1827.92  4879.1 1825.51  4909.2 1822.68  4949.4 1823.19  4971.5 1822.05
  4987.5 1815.87  4987.7 1815.37  4991.5 1815.87  5009.5 1818.53  5019.6 1822.19
  5029.6 1829.33  5049.7 1832.74  5059.7 1841.43  5079.7 1850.16  5089.8 1853.15
  5099.8 1854.85  5129.9 1862.22  5160.0 1870.52  5165.5 1873.86  5180.9 1876.23
#Mann=3,-1,0
  4641.7     0.1       0  4987.5    0.05       0  4991.5     0.1       0
Bank Sta=4987.5,4991.5
Exp/Cntr=0.3,0.1

Type RM Length L Ch R = 1,2269,450,450,450
BEGIN DESCRIPTION:
Stream0217 5.0
END DESCRIPTION:
XS GIS Cut Line= 3
      1860225.00     13942625.00      1860025.00     13942525.00
      1859725.01     13942375.01
#Sta/Elev= 30
  4776.5 1882.48  4812.8 1871.57  4874.3 1849.71  4919.0 1835.94  4924.6 1835.45
  4941.4 1829.01  4947.0 1828.38  4986.1 1810.08  5002.9 1808.47  5008.5 1806.24
  5014.1 1807.54  5020.5 1804.23  5020.7 1803.73  5024.5 1804.23  5030.9 1806.88
  5036.4 1806.73  5044.8 1815.81  5067.2 1817.92  5075.6 1820.97  5081.2 1821.23
  5089.5 1824.75  5097.9 1826.46  5103.5 1826.00  5148.2 1836.95  5187.4 1849.36
  5237.7 1862.95  5254.5 1870.60  5282.4 1877.07  5290.8 1880.50  5335.5 1892.29
#Mann=3,-1,0
  4776.5     0.1       0  5020.5    0.05       0  5024.5     0.1       0
Bank Sta=5020.5,5024.5
Exp/Cntr=0.3,0.1

Type RM Length L Ch R = 1,1819,435,435,435
BEGIN DESCRIPTION:
Stream0217 4.0
END DESCRIPTION:
XS GIS Cut Line= 3
      1860212.06     13942310.98      1860042.23     13942126.34
      1859875.01     13942125.00
#Sta/Elev= 30
  4689.3 1837.18  4691.5 1835.97  4698.3 1835.08  4719.8 1833.72  4726.6 1831.21
  4740.8 1829.41  4806.5 1824.69  4811.7 1823.54  4833.3 1821.75  4875.2 1815.26
  4889.4 1812.80  4896.8 1810.48  4903.6 1810.24  4911.0 1807.99  4917.8 1807.79
  4925.2 1805.51  4931.9 1804.96  4937.7 1802.53  4967.4 1798.83  4987.4 1799.16
  5002.6 1796.84  5005.4 1796.64  5005.7 1796.14  5009.4 1796.64  5027.4 1802.24
  5037.4 1807.74  5047.4 1813.71  5087.4 1844.28  5104.9 1851.17  5107.4 1851.17
#Mann=5,-1,0
  4689.3     0.1       0  4806.5    0.07       0  5002.6     0.1       0
  5005.4    0.05       0  5009.4     0.1       0
Bank Sta=5005.4,5009.4
Exp/Cntr=0.3,0.1

Type RM Length L Ch R = 1,1384,455,455,455
BEGIN DESCRIPTION:
Stream0217 3.0
END DESCRIPTION:
XS GIS Cut Line= 3
      1860325.03     13941825.01      1860175.00     13941775.00
      1859925.00     13941875.00
#Sta/Elev= 30
  4835.7 1844.75  4838.4 1844.75  4867.4 1834.42  4877.9 1826.48  4899.0 1813.02
  4920.1 1801.18  4972.8 1783.36  4981.3 1783.05  4981.6 1782.55  4985.3 1783.05
  5003.3 1784.94  5008.7 1783.75  5015.4 1787.88  5026.2 1792.17  5032.9 1796.16
  5038.3 1793.79  5047.7 1795.60  5062.5 1795.24  5111.9 1797.61  5133.9 1799.65
  5164.8 1805.80  5170.2 1805.95  5176.9 1808.46  5185.8 1809.92  5194.4 1812.12
  5199.8 1811.90  5218.7 1815.45  5224.1 1815.19  5248.3 1818.82  5263.1 1819.95
#Mann=5,-1,0
  4835.7    0.07       0  4981.3    0.05       0  4985.3    0.07       0
  5111.9     0.1       0  5185.8    0.07       0
Bank Sta=4981.3,4985.3
Exp/Cntr=0.3,0.1

Type RM Length L Ch R = 1,929,421,421,421
BEGIN DESCRIPTION:
Stream0217 2.0
END DESCRIPTION:
XS GIS Cut Line= 3
      1860324.98     13941425.00      1860025.00     13941375.00
      1859925.02     13941375.00
#Sta/Elev= 30
  4700.6 1828.86  4703.1 1828.86  4728.5 1822.81  4733.5 1822.63  4741.1 1820.78
  4771.5 1815.33  4781.7 1814.27  4794.4 1811.56  4812.1 1806.18  4842.5 1798.90
  4862.8 1791.56  4883.1 1782.63  4893.2 1779.68  4910.9 1776.77  4916.0 1779.33
  4933.8 1782.56  4943.9 1782.15  4971.8 1774.47  4992.6 1773.04  4992.8 1772.54
  4996.3 1772.54  4996.6 1773.04  5024.7 1773.38  5034.7 1774.13  5044.7 1777.26
  5054.7 1783.05  5064.7 1789.93  5074.7 1794.65  5084.7 1797.68  5104.7 1799.83
#Mann=3,-1,0
  4700.6     0.1       0  4992.6    0.05       0  4996.6     0.1       0
Bank Sta=4992.6,4996.6
Exp/Cntr=0.3,0.1

Type RM Length L Ch R = 1,508,0,0,0
BEGIN DESCRIPTION:
Stream0217 1.0
END DESCRIPTION:
XS GIS Cut Line= 4
      1860325.04     13941075.01      1859931.35     13940987.52
      1859830.55     13941030.57      1859675.00     13941225.00
#Sta/Elev= 30
  4563.6 1798.65  4582.8 1798.10  4588.0 1796.37  4604.6 1795.19  4631.5 1795.16
  4636.6 1790.64  4655.8 1788.96  4666.1 1786.40  4675.0 1783.34  4680.2 1778.70
  4686.6 1776.61  4717.3 1771.90  4723.7 1770.24  4728.8 1767.05  4758.3 1764.48
  4797.9 1764.00  4901.7 1763.47  4968.8 1761.47  4969.0 1760.97  4972.8 1761.47
  4990.3 1762.16  5126.2 1768.28  5140.6 1771.38  5155.4 1776.23  5183.8 1783.80
  5219.0 1791.20  5247.9 1800.62  5275.2 1804.85  5311.9 1810.19  5325.5 1810.84
#Mann=7,-1,0
  4563.6     0.1       0  4797.9   0.035       0  4968.8    0.05       0
  4972.8   0.035       0  4990.3     0.1       0  5155.4    0.07       0
  5275.2   0.035       0
Bank Sta=4968.8,4972.8
Exp/Cntr=0.3,0.1

Chan Stop Cuts=-1