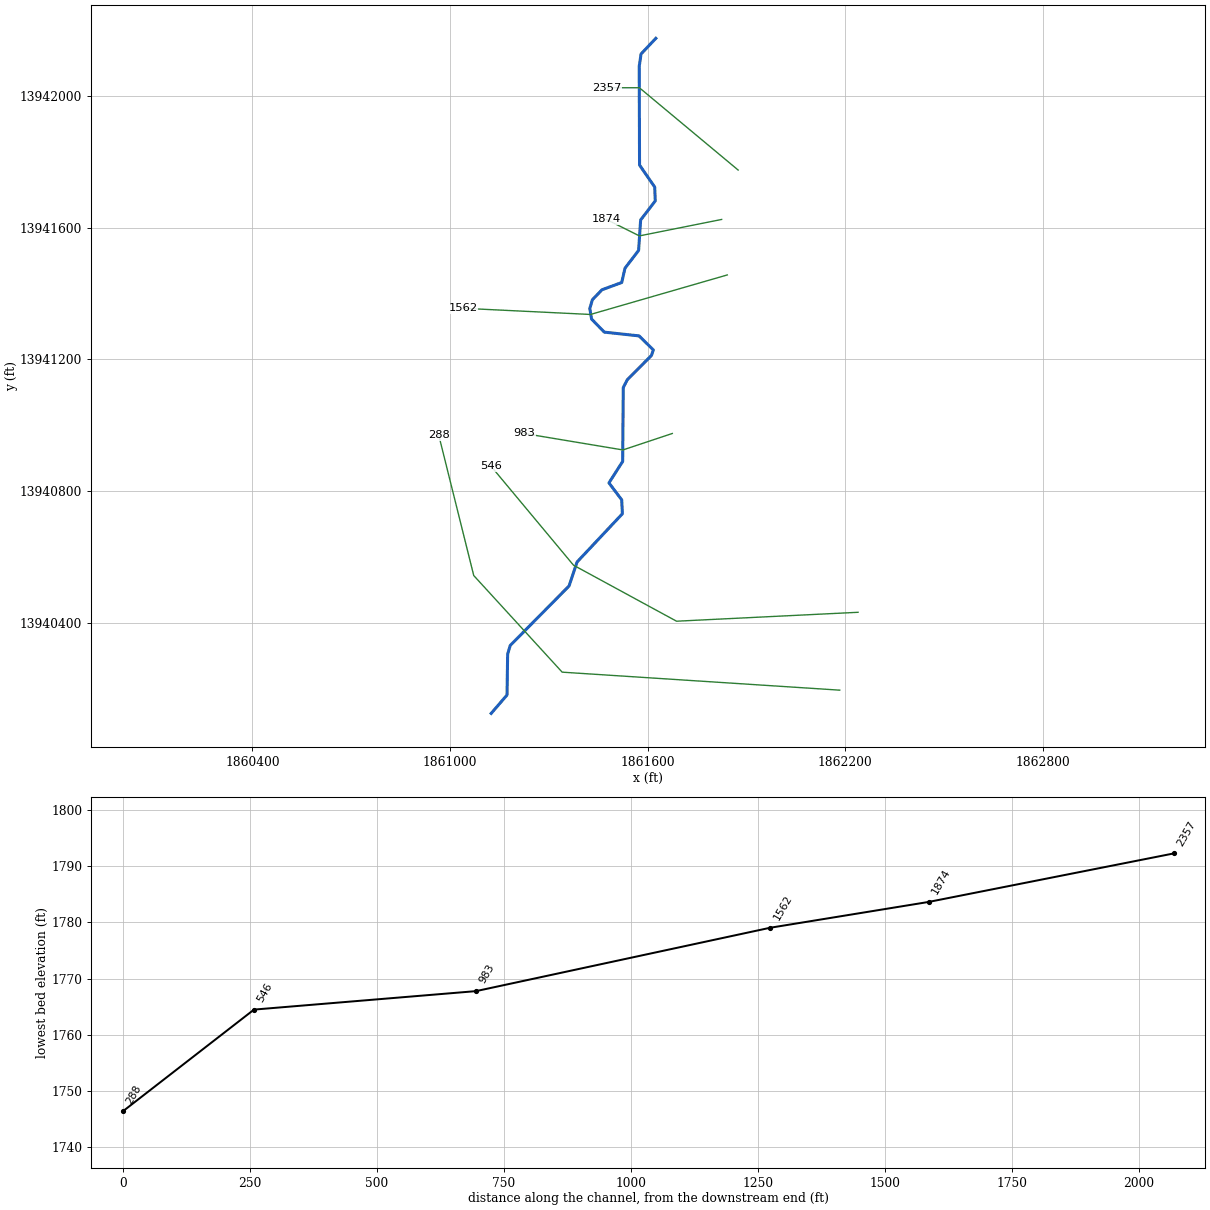
--- Stream0218.prj (project) ---

Proj Title=Stream0218 Base Level Engineering
Current Plan=p01
Default Exp/Contr=0.3,0.1
English Units
Geom File=g01
Flow File=f01
Plan File=p01
BEGIN DESCRIPTION:
Stream0218
END DESCRIPTION:

--- Stream0218.p01 (plan) ---

Plan Title=Multiple Run
Short Identifier=Multiple
Geom File=g01
Flow File=f01
Subcritical Flow
K Sum by GR= 0
Std Step Tol= 0.01
Critical Tol= 0.01
Num of Std Step Trials= 20
Max Error Tol= 0.3
Flow Tol Ratio= 0.001
Split Flow NTrial= 30
Split Flow Tol= 0.02
Split Flow Ratio= 0.02
Log Output Level= 0
Friction Slope Method= 1
Unsteady Friction Slope Method= 2
Unsteady Bridges Friction Slope Method= 1
Parabolic Critical Depth
Global Vel Dist=  1 , 1 , 1
Global Log Level= 0
CheckData=True
Encroach Param= -1, 0, 0, 0
BEGIN DESCRIPTION:
Multiple Run
END DESCRIPTION:

--- Stream0218.f01 (steady flow) ---

Flow Title=Multiple
Number of Profiles=7
Profile Names=10-year,25-year,50-year,1pct_min,100-year,1pct_plu,500-year
River Rch & RM= Stream0218,Reach-1,2357
    1217    2114    2985    2041    4071    8124    7478
Boundary for River Rch & Prof#=Stream0218,Reach-1,1
Up Type=0
Dn Type=3
Dn Slope=0.005
Boundary for River Rch & Prof#=Stream0218,Reach-1,2
Up Type=0
Dn Type=3
Dn Slope=0.005
Boundary for River Rch & Prof#=Stream0218,Reach-1,3
Up Type=0
Dn Type=3
Dn Slope=0.005
Boundary for River Rch & Prof#=Stream0218,Reach-1,4
Up Type=0
Dn Type=3
Dn Slope=0.005
Boundary for River Rch & Prof#=Stream0218,Reach-1,5
Up Type=0
Dn Type=3
Dn Slope=0.005
Boundary for River Rch & Prof#=Stream0218,Reach-1,6
Up Type=0
Dn Type=3
Dn Slope=0.005
Boundary for River Rch & Prof#=Stream0218,Reach-1,7
Up Type=0
Dn Type=3
Dn Slope=0.005

--- Stream0218.g01 (geometry) ---

Geom Title=Existing Conditions

River Reach=Stream0218,Reach-1
Reach XY= 30
      1861625.00     13942175.00      1861580.14     13942127.59
      1861574.59     13942090.17      1861575.54     13941790.21
      1861621.63     13941723.26      1861623.18     13941681.12
      1861578.89     13941623.41      1861572.68     13941530.94
      1861531.27     13941476.84      1861521.46     13941433.49
      1861461.52     13941411.42      1861432.38     13941381.29
      1861424.46     13941354.86      1861429.94     13941322.45
      1861468.45     13941282.75      1861573.99     13941271.38
      1861617.52     13941228.62      1861611.61     13941211.80
      1861538.43     13941138.32      1861526.06     13941114.57
      1861524.34     13940890.16      1861482.59     13940824.99
      1861521.43     13940773.35      1861523.34     13940731.05
      1861385.78     13940584.68      1861361.37     13940511.79
      1861182.81     13940331.19      1861174.97     13940305.01
      1861173.09     13940180.79      1861125.00     13940125.00

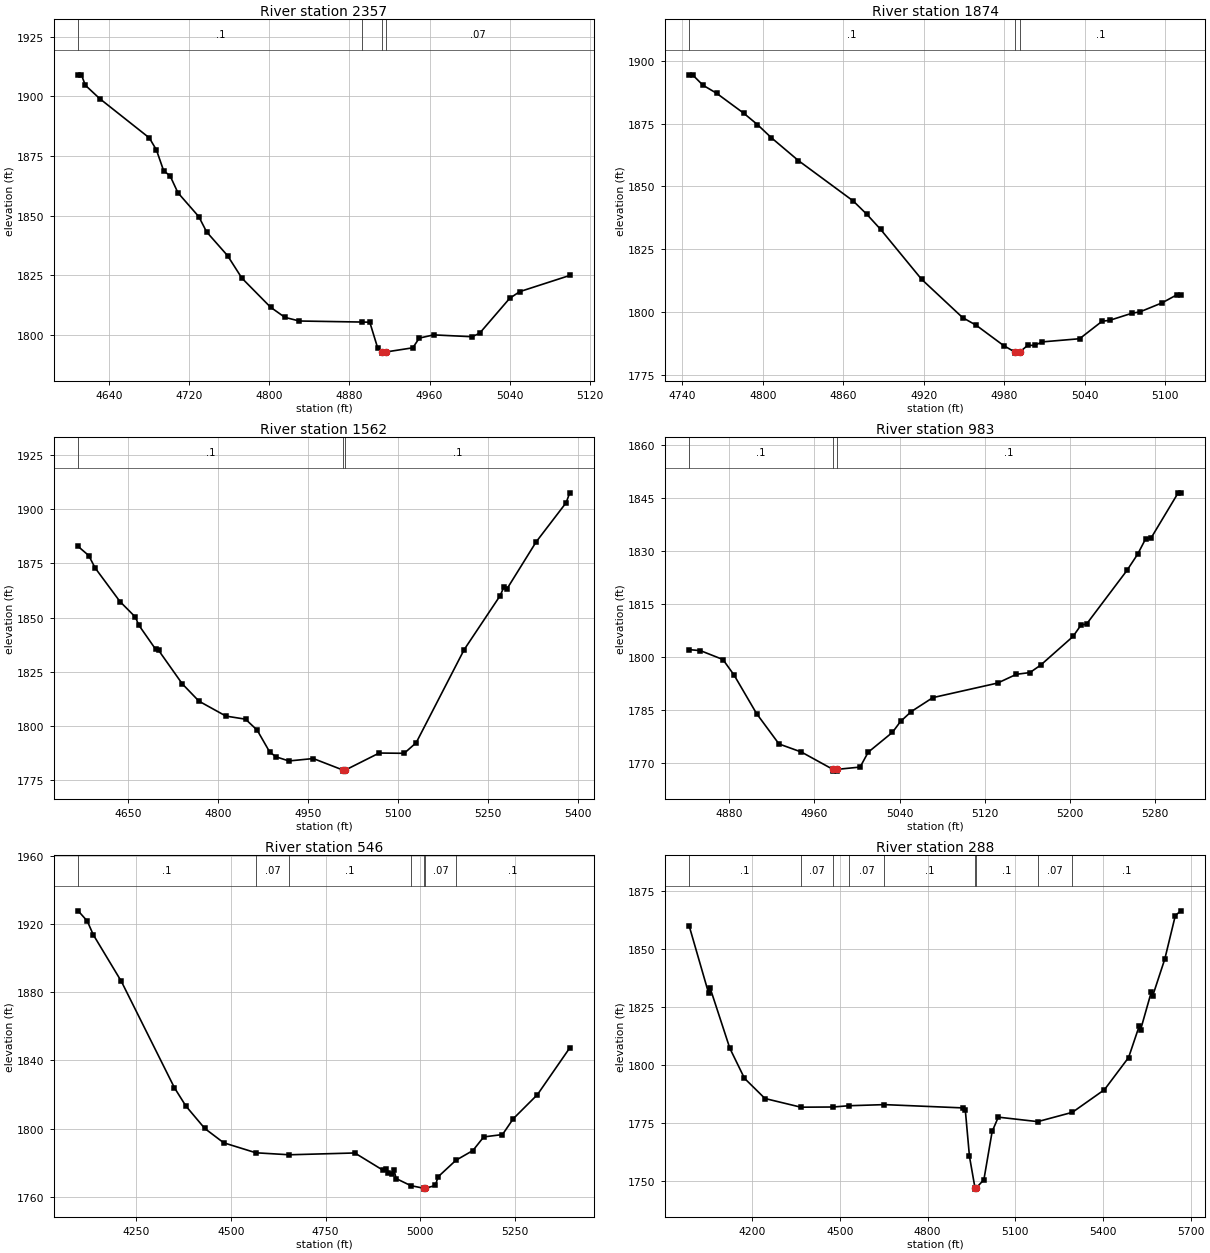
Type RM Length L Ch R = 1,2357,483,483,483
BEGIN DESCRIPTION:
Stream0218 5.0
END DESCRIPTION:
XS GIS Cut Line= 3
      1861875.02     13941774.99      1861575.00     13942025.00
      1861475.03     13942025.00
#Sta/Elev= 30
  4609.4 1909.01  4612.7 1909.01  4616.6 1904.64  4630.9 1899.04  4680.4 1882.57
  4687.5 1877.54  4694.7 1868.81  4701.2 1866.61  4709.0 1859.54  4729.8 1849.54
  4737.6 1843.14  4758.5 1833.18  4772.8 1823.75  4801.4 1811.56  4815.7 1807.30
  4830.1 1805.77  4893.1 1805.33  4900.4 1805.27  4908.2 1794.57  4912.7 1792.80
  4912.9 1792.30  4916.7 1792.80  4943.3 1794.53  4949.8 1798.60  4964.1 1799.95
  5002.4 1799.18  5009.9 1800.60  5039.9 1815.24  5049.9 1818.07  5099.9 1824.87
#Mann=4,-1,0
  4609.4     0.1       0  4893.1    0.07       0  4912.7    0.05       0
  4916.7    0.07       0
Bank Sta=4912.7,4916.7
Exp/Cntr=0.3,0.1

Type RM Length L Ch R = 1,1874,312,312,312
BEGIN DESCRIPTION:
Stream0218 4.0
END DESCRIPTION:
XS GIS Cut Line= 3
      1861824.96     13941624.99      1861575.00     13941575.00
      1861475.01     13941624.99
#Sta/Elev= 30
  4745.1 1894.42  4747.6 1894.42  4755.3 1890.31  4765.5 1887.09  4785.9 1879.08
  4796.0 1874.61  4806.2 1869.46  4826.6 1860.26  4867.4 1844.22  4877.6 1838.90
  4887.8 1832.94  4918.4 1813.06  4949.0 1797.80  4959.2 1794.73  4979.6 1786.67
  4987.8 1784.15  4988.1 1783.65  4991.6 1783.65  4991.8 1784.15  4997.5 1786.74
  5002.8 1786.74  5008.4 1788.12  5036.3 1789.38  5053.1 1796.35  5058.7 1796.70
  5075.5 1799.56  5081.1 1800.03  5097.8 1803.66  5109.0 1806.91  5111.8 1806.91
#Mann=3,-1,0
  4745.1     0.1       0  4987.8    0.05       0  4991.8     0.1       0
Bank Sta=4987.8,4991.8
Exp/Cntr=0.3,0.1

Type RM Length L Ch R = 1,1562,579,579,579
BEGIN DESCRIPTION:
Stream0218 3.0
END DESCRIPTION:
XS GIS Cut Line= 3
      1861842.04     13941456.47      1861426.49     13941336.45
      1861038.98     13941355.23
#Sta/Elev= 30
  4566.3 1882.82  4584.0 1878.63  4594.6 1872.93  4636.1 1857.39  4661.9 1850.19
  4667.3 1846.60  4695.5 1835.40  4700.7 1834.81  4740.2 1819.34  4768.0 1811.36
  4813.0 1804.47  4845.7 1803.04  4865.1 1797.99  4885.9 1787.95  4896.3 1785.68
  4918.1 1783.75  4958.8 1784.86  5008.3 1779.55  5008.6 1779.05  5012.3 1779.55
  5068.8 1787.41  5110.5 1787.28  5130.5 1792.16  5210.6 1835.16  5270.6 1860.07
  5277.2 1864.24  5282.2 1863.30  5330.7 1884.91  5380.8 1903.03  5386.8 1907.59
#Mann=3,-1,0
  4566.3     0.1       0  5008.3    0.05       0  5012.3     0.1       0
Bank Sta=5008.3,5012.3
Exp/Cntr=0.3,0.1

Type RM Length L Ch R = 1,983,437,437,437
BEGIN DESCRIPTION:
Stream0218 2.0
END DESCRIPTION:
XS GIS Cut Line= 3
      1861675.04     13940975.01      1861525.00     13940925.00
      1861225.00     13940975.00
#Sta/Elev= 30
  4842.2 1802.14  4852.8 1801.85  4873.9 1799.34  4884.4 1794.93  4905.5 1784.06
  4926.6 1775.45  4947.7 1773.16  4977.3 1768.26  4977.5 1767.76  4981.0 1767.76
  4981.3 1768.26  5002.9 1768.91  5010.5 1773.11  5033.3 1778.73  5040.9 1781.81
  5051.0 1784.61  5071.3 1788.56  5132.2 1792.68  5149.9 1795.16  5162.6 1795.65
  5172.7 1797.76  5203.1 1805.86  5210.7 1809.13  5215.8 1809.36  5253.8 1824.54
  5263.9 1829.15  5271.5 1833.55  5276.6 1833.77  5302.0 1846.51  5304.5 1846.51
#Mann=3,-1,0
  4842.2     0.1       0  4977.3    0.05       0  4981.3     0.1       0
Bank Sta=4977.3,4981.3
Exp/Cntr=0.3,0.1

Type RM Length L Ch R = 1,546,258,258,258
BEGIN DESCRIPTION:
Stream0218 1.0
END DESCRIPTION:
XS GIS Cut Line= 4
      1862239.15     13940431.98      1861687.86     13940404.90
      1861375.00     13940575.00      1861124.98     13940875.02
#Sta/Elev= 30
  4096.3 1927.58  4120.5 1921.58  4136.1 1913.65  4210.6 1886.18  4350.8 1823.85
  4380.8 1813.22  4430.9 1800.01  4480.9 1791.62  4565.9 1785.77  4654.3 1784.60
  4827.2 1785.66  4901.9 1775.51  4908.9 1776.48  4914.6 1773.71  4924.7 1773.12
  4930.7 1775.70  4936.4 1770.66  4974.8 1766.54  5009.5 1764.97  5009.8 1764.47
  5013.5 1764.97  5040.2 1766.63  5046.7 1771.60  5094.3 1781.38  5139.1 1787.09
  5167.7 1795.07  5217.2 1796.45  5245.8 1805.74  5309.6 1819.87  5394.9 1847.24
#Mann=7,-1,0
  4096.3     0.1       0  4565.9    0.07       0  4654.3     0.1       0
  4974.8    0.07       0  5009.5    0.05       0  5013.5    0.07       0
  5094.3     0.1       0
Bank Sta=5009.5,5013.5
Exp/Cntr=0.3,0.1

Type RM Length L Ch R = 1,288,0,0,0
BEGIN DESCRIPTION:
Stream0218 0.0
END DESCRIPTION:
XS GIS Cut Line= 4
      1862183.57     13940195.50      1861340.55     13940250.17
      1861072.03     13940543.58      1860965.81     13940969.61
#Sta/Elev= 30
  3984.8 1859.69  4051.4 1830.66  4056.4 1832.97  4123.7 1807.05  4173.8 1794.10
  4243.9 1785.40  4366.7 1781.66  4476.4 1781.74  4531.6 1782.29  4652.7 1782.77
  4921.8 1781.35  4929.2 1780.39  4943.4 1760.45  4962.3 1746.86  4962.6 1746.36
  4966.3 1746.86  4992.7 1750.41  5021.0 1771.19  5042.0 1777.37  5176.9 1775.44
  5295.4 1779.45  5405.1 1789.20  5487.7 1803.06  5523.8 1816.55  5528.9 1815.09
  5565.1 1831.18  5570.2 1829.63  5611.5 1845.47  5647.6 1864.24  5666.4 1866.26
#Mann=9,-1,0
  3984.8     0.1       0  4366.7    0.07       0  4476.4     0.1       0
  4531.6    0.07       0  4652.7     0.1       0  4962.3    0.05       0
  4966.3     0.1       0  5176.9    0.07       0  5295.4     0.1       0
Bank Sta=4962.3,4966.3
Exp/Cntr=0.3,0.1

Chan Stop Cuts=-1