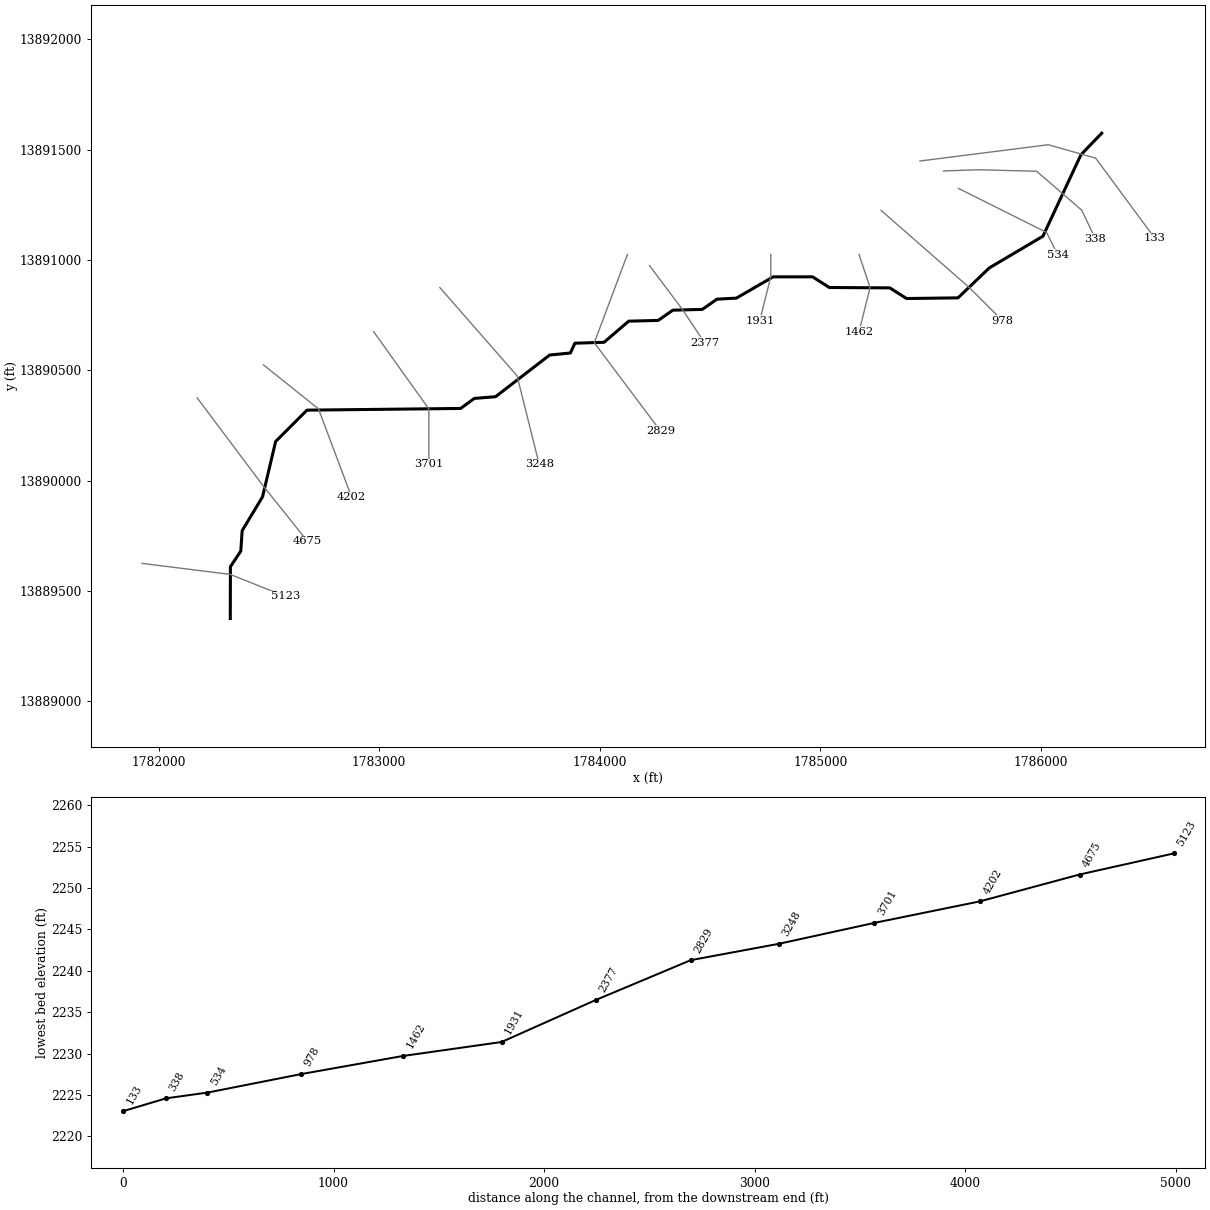
--- Stream0219.prj (project) ---

Proj Title=Stream0219 Base Level Engineering
Current Plan=p01
Default Exp/Contr=0.3,0.1
English Units
Geom File=g01
Flow File=f01
Plan File=p01
BEGIN DESCRIPTION:
Stream0219
END DESCRIPTION:

--- Stream0219.p01 (plan) ---

Plan Title=Multiple Run
Short Identifier=Multiple
Geom File=g01
Flow File=f01
Subcritical Flow
K Sum by GR= 0
Std Step Tol= 0.01
Critical Tol= 0.01
Num of Std Step Trials= 20
Max Error Tol= 0.3
Flow Tol Ratio= 0.001
Split Flow NTrial= 30
Split Flow Tol= 0.02
Split Flow Ratio= 0.02
Log Output Level= 0
Friction Slope Method= 1
Unsteady Friction Slope Method= 2
Unsteady Bridges Friction Slope Method= 1
Parabolic Critical Depth
Global Vel Dist=  1 , 1 , 1
Global Log Level= 0
CheckData=True
Encroach Param= -1, 0, 0, 0
BEGIN DESCRIPTION:
Multiple Run
END DESCRIPTION:

--- Stream0219.f01 (steady flow) ---

Flow Title=Multiple
Number of Profiles=7
Profile Names=10-year,25-year,50-year,1pct_min,100-year,1pct_plu,500-year
River Rch & RM= Stream0219,Reach-1,5123
    1614    2798    3937    2670    5328   10631    9659
Boundary for River Rch & Prof#=Stream0219,Reach-1,1
Up Type=0
Dn Type=3
Dn Slope=0.005
Boundary for River Rch & Prof#=Stream0219,Reach-1,2
Up Type=0
Dn Type=3
Dn Slope=0.005
Boundary for River Rch & Prof#=Stream0219,Reach-1,3
Up Type=0
Dn Type=3
Dn Slope=0.005
Boundary for River Rch & Prof#=Stream0219,Reach-1,4
Up Type=0
Dn Type=3
Dn Slope=0.005
Boundary for River Rch & Prof#=Stream0219,Reach-1,5
Up Type=0
Dn Type=3
Dn Slope=0.005
Boundary for River Rch & Prof#=Stream0219,Reach-1,6
Up Type=0
Dn Type=3
Dn Slope=0.005
Boundary for River Rch & Prof#=Stream0219,Reach-1,7
Up Type=0
Dn Type=3
Dn Slope=0.005

--- Stream0219.g01 (geometry) ---

Geom Title=Existing Conditions

River Reach=Stream0219,Reach-1
Reach XY= 30
      1782325.00     13889375.00      1782325.52     13889609.78
      1782372.64     13889680.98      1782378.83     13889773.42
      1782471.17     13889926.58      1782530.52     13890177.43
      1782672.55     13890319.54      1783369.06     13890327.26
      1783430.98     13890372.64      1783527.42     13890380.54
      1783772.64     13890569.44      1783866.50     13890578.56
      1783886.97     13890623.02      1784019.13     13890627.08
      1784130.86     13890722.92      1784264.49     13890726.23
      1784330.94     13890772.73      1784464.49     13890776.23
      1784530.98     13890822.64      1784619.03     13890827.33
      1784785.50     13890923.80      1784964.49     13890923.78
      1785040.22     13890875.52      1785314.50     13890873.78
      1785390.22     13890825.52      1785623.54     13890828.54
      1785765.32     13890964.22      1786008.51     13891107.95
      1786180.79     13891477.32      1786275.00     13891575.00

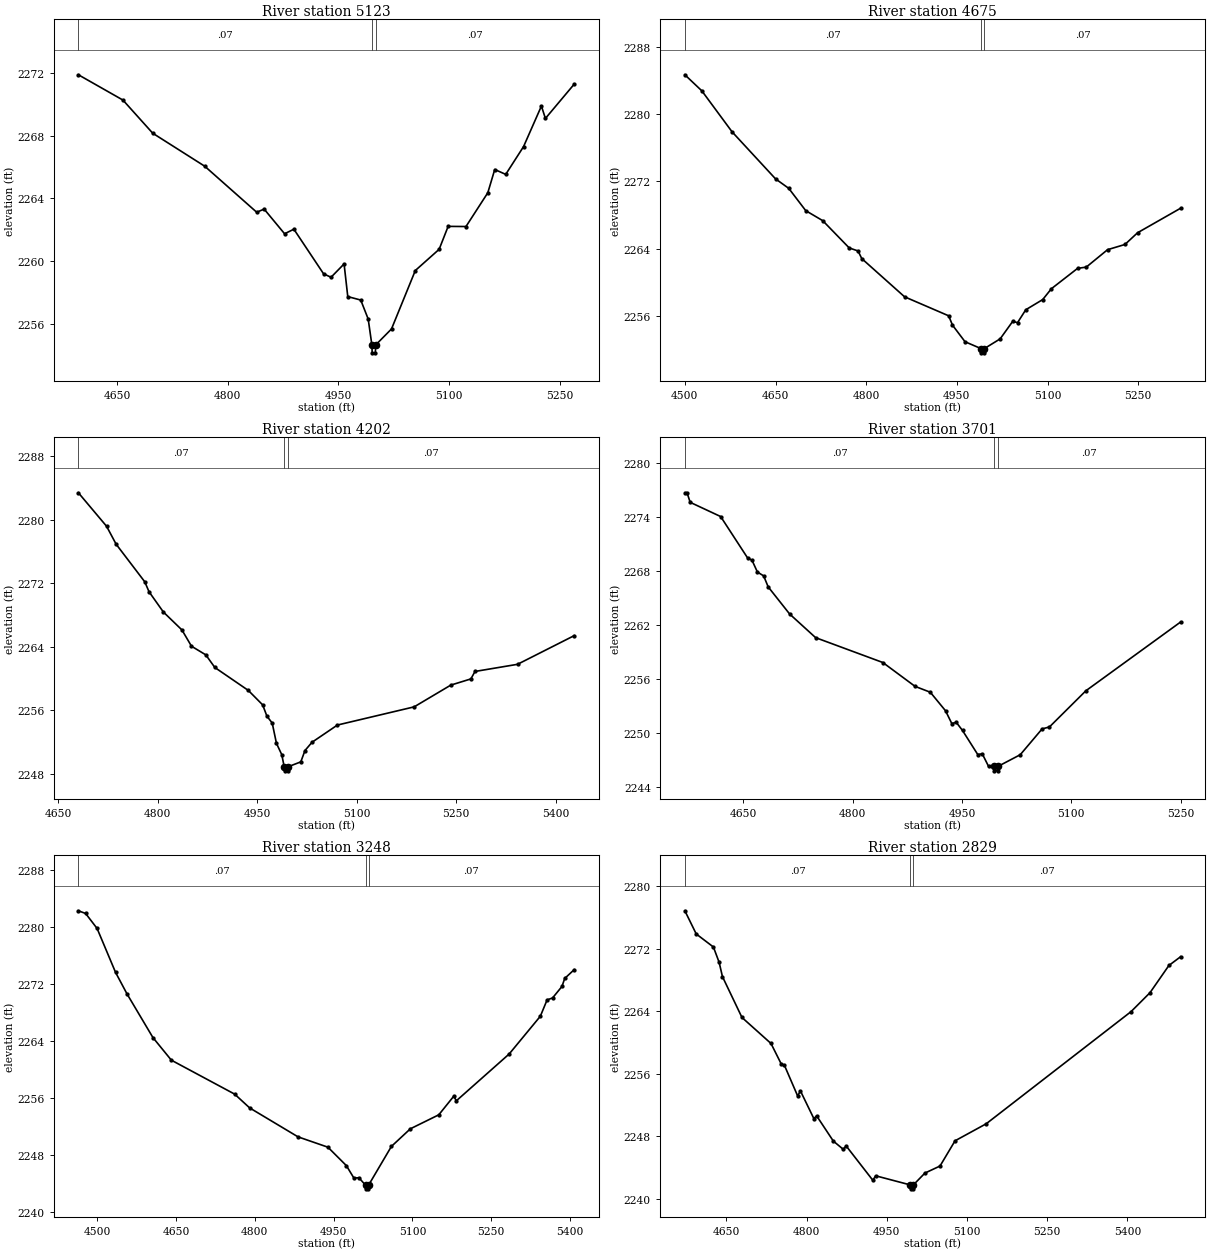
Type RM Length L Ch R = 1,5123,448,448,448
BEGIN DESCRIPTION:
Stream0219 11.0
END DESCRIPTION:
XS GIS Cut Line= 3
      1781925.03     13889625.00      1782325.00     13889575.00
      1782574.96     13889475.02
#Sta/Elev= 30
  4597.3 2271.87  4657.7 2270.26  4698.1 2268.15  4768.6 2266.05  4839.1 2263.12
  4849.2 2263.32  4876.9 2261.75  4889.5 2262.04  4929.8 2259.20  4939.9 2258.98
  4957.6 2259.83  4962.6 2257.75  4980.2 2257.53  4990.3 2256.32  4995.3 2254.67
  4995.7 2254.17  5000.0 2254.17  5000.4 2254.67  5021.9 2255.69  5054.2 2259.41
  5086.5 2260.76  5098.7 2262.22  5122.9 2262.21  5152.5 2264.36  5161.9 2265.84
  5176.8 2265.53  5201.0 2267.30  5225.2 2269.88  5230.6 2269.09  5269.6 2271.27
#Mann=3,-1,0
  4597.3    0.07       0  4995.3    0.05       0  5000.4    0.07       0
Bank Sta=4995.3,5000.4
Exp/Cntr=0.3,0.1

Type RM Length L Ch R = 1,4675,473,473,473
BEGIN DESCRIPTION:
Stream0219 10.0
END DESCRIPTION:
XS GIS Cut Line= 3
      1782175.00     13890375.00      1782475.00     13889975.00
      1782675.03     13889724.96
#Sta/Elev= 30
  4500.0 2284.67  4528.1 2282.76  4578.1 2277.89  4650.0 2272.30  4671.9 2271.17
  4700.0 2268.52  4728.1 2267.33  4771.9 2264.09  4786.5 2263.73  4792.7 2262.82
  4863.5 2258.28  4936.5 2256.02  4942.7 2254.92  4963.5 2252.94  4990.1 2252.12
  4990.5 2251.62  4995.0 2251.62  4995.4 2252.12  5021.6 2253.28  5042.4 2255.36
  5050.4 2255.21  5064.0 2256.74  5092.0 2257.95  5106.4 2259.24  5149.7 2261.66
  5164.1 2261.81  5199.3 2263.88  5228.1 2264.50  5248.9 2265.89  5320.2 2268.81
#Mann=3,-1,0
  4500.0    0.07       0  4990.1    0.05       0  4995.4    0.07       0
Bank Sta=4990.1,4995.4
Exp/Cntr=0.3,0.1

Type RM Length L Ch R = 1,4202,501,501,501
BEGIN DESCRIPTION:
Stream0219 9.0
END DESCRIPTION:
XS GIS Cut Line= 3
      1782474.96     13890525.03      1782725.00     13890325.00
      1782875.00     13889925.00
#Sta/Elev= 30
  4680.5 2283.41  4723.0 2279.19  4737.4 2276.93  4780.6 2272.19  4787.0 2270.94
  4808.6 2268.39  4836.6 2266.13  4851.0 2264.08  4872.6 2262.99  4886.2 2261.40
  4936.7 2258.51  4958.3 2256.69  4964.7 2255.27  4972.7 2254.40  4979.1 2251.84
  4987.1 2250.42  4990.8 2248.88  4991.3 2248.38  4995.8 2248.38  4996.2 2248.88
  5015.8 2249.51  5022.1 2250.94  5032.7 2251.98  5071.0 2254.15  5186.7 2256.44
  5241.9 2259.18  5272.2 2259.96  5278.4 2260.90  5342.5 2261.80  5427.9 2265.41
#Mann=3,-1,0
  4680.5    0.07       0  4990.8    0.05       0  4996.2    0.07       0
Bank Sta=4990.8,4996.2
Exp/Cntr=0.3,0.1

Type RM Length L Ch R = 1,3701,453,453,453
BEGIN DESCRIPTION:
Stream0219 8.0
END DESCRIPTION:
XS GIS Cut Line= 3
      1782975.02     13890674.97      1783225.00     13890325.00
      1783225.00     13890074.98
#Sta/Elev= 30
  4569.9 2276.66  4572.9 2276.66  4577.2 2275.60  4619.0 2274.02  4655.9 2269.43
  4662.0 2269.17  4669.4 2267.86  4678.0 2267.43  4684.2 2266.21  4713.6 2263.20
  4749.3 2260.57  4841.5 2257.81  4885.7 2255.16  4906.6 2254.51  4927.5 2252.45
  4936.1 2251.03  4942.2 2251.17  4950.8 2250.26  4971.7 2247.59  4977.9 2247.67
  4986.5 2246.28  4994.2 2246.28  4994.6 2245.78  4999.2 2245.78  4999.6 2246.28
  5030.0 2247.57  5060.0 2250.44  5070.0 2250.65  5120.0 2254.67  5250.0 2262.31
#Mann=3,-1,0
  4569.9    0.07       0  4994.2    0.05       0  4999.6    0.07       0
Bank Sta=4994.2,4999.6
Exp/Cntr=0.3,0.1

Type RM Length L Ch R = 1,3248,419,419,419
BEGIN DESCRIPTION:
Stream0219 7.0
END DESCRIPTION:
XS GIS Cut Line= 3
      1783275.00     13890875.00      1783625.00     13890475.00
      1783725.00     13890075.01
#Sta/Elev= 30
  4464.1 2282.25  4477.9 2281.87  4499.7 2279.77  4534.8 2273.62  4556.6 2270.60
  4606.0 2264.47  4641.1 2261.30  4761.6 2256.54  4790.1 2254.61  4882.2 2250.55
  4939.1 2249.10  4974.2 2246.52  4988.5 2244.78  4998.2 2244.81  5010.9 2243.76
  5011.3 2243.26  5015.9 2243.26  5016.4 2243.76  5060.0 2249.21  5096.1 2251.68
  5150.2 2253.64  5178.6 2256.24  5183.7 2255.61  5284.2 2262.17  5343.5 2267.46
  5356.4 2269.76  5366.7 2270.02  5384.7 2271.64  5389.9 2272.76  5407.9 2273.99
#Mann=3,-1,0
  4464.1    0.07       0  5010.9    0.05       0  5016.4    0.07       0
Bank Sta=5010.9,5016.4
Exp/Cntr=0.3,0.1

Type RM Length L Ch R = 1,2829,452,452,452
BEGIN DESCRIPTION:
Stream0219 6.0
END DESCRIPTION:
XS GIS Cut Line= 3
      1784124.99     13891024.98      1783975.00     13890625.00
      1784275.02     13890224.98
#Sta/Elev= 30
  4572.4 2276.88  4593.7 2273.91  4625.8 2272.24  4636.5 2270.28  4642.7 2268.45
  4679.2 2263.22  4733.5 2259.89  4753.0 2257.22  4758.4 2257.13  4783.3 2253.18
  4788.6 2253.81  4813.6 2250.28  4818.9 2250.62  4850.1 2247.39  4868.7 2246.34
  4874.1 2246.77  4923.9 2242.38  4929.3 2242.95  4994.1 2241.78  4994.6 2241.28
  4999.3 2241.28  4999.7 2241.78  5021.4 2243.30  5049.6 2244.20  5077.7 2247.43
  5136.0 2249.61  5406.9 2263.97  5442.3 2266.39  5477.7 2269.88  5499.6 2271.00
#Mann=3,-1,0
  4572.4    0.07       0  4994.1    0.05       0  4999.7    0.07       0
Bank Sta=4994.1,4999.7
Exp/Cntr=0.3,0.1

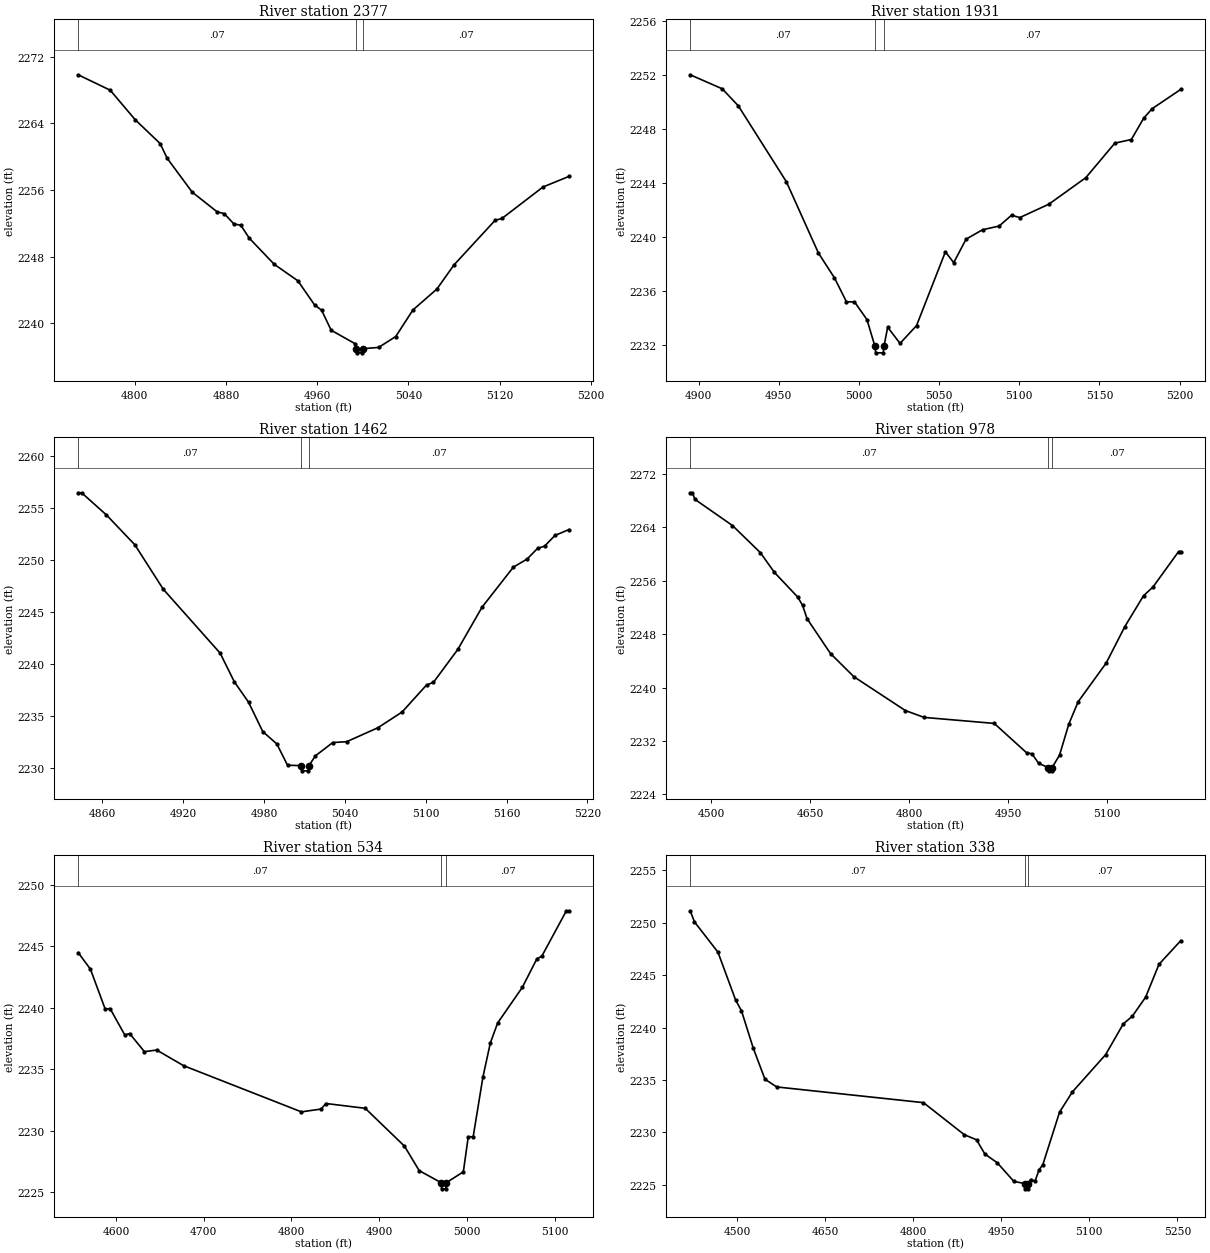
Type RM Length L Ch R = 1,2377,446,446,446
BEGIN DESCRIPTION:
Stream0219 5.0
END DESCRIPTION:
XS GIS Cut Line= 3
      1784225.00     13890974.99      1784375.00     13890775.00
      1784475.02     13890624.98
#Sta/Elev= 30
  4750.4 2269.85  4778.5 2268.00  4800.4 2264.46  4822.3 2261.59  4828.5 2259.82
  4850.4 2255.76  4872.3 2253.39  4878.5 2253.18  4886.9 2251.95  4893.1 2251.77
  4900.4 2250.24  4922.3 2247.10  4943.1 2245.11  4957.7 2242.22  4963.9 2241.58
  4972.3 2239.17  4993.1 2237.57  4994.5 2236.96  4994.9 2236.46  4999.6 2236.46
  5000.1 2236.96  5013.9 2237.11  5028.9 2238.42  5044.0 2241.61  5065.0 2244.12
  5080.0 2247.02  5116.1 2252.38  5122.1 2252.60  5158.1 2256.38  5180.7 2257.64
#Mann=3,-1,0
  4750.4    0.07       0  4994.5    0.05       0  5000.1    0.07       0
Bank Sta=4994.5,5000.1
Exp/Cntr=0.3,0.1

Type RM Length L Ch R = 1,1931,469,469,469
BEGIN DESCRIPTION:
Stream0219 4.0
END DESCRIPTION:
XS GIS Cut Line= 3
      1784775.00     13891024.96      1784775.00     13890925.00
      1784725.00     13890725.02
#Sta/Elev= 30
  4894.7 2252.02  4914.7 2250.98  4924.7 2249.72  4954.7 2244.09  4974.7 2238.80
  4984.7 2236.96  4992.2 2235.18  4997.2 2235.18  5005.0 2233.86  5009.9 2231.90
  5010.4 2231.40  5015.1 2231.40  5015.6 2231.90  5017.9 2233.30  5025.6 2232.10
  5035.9 2233.42  5053.9 2238.89  5059.1 2238.09  5066.8 2239.83  5077.1 2240.53
  5087.4 2240.80  5095.2 2241.61  5100.3 2241.43  5118.4 2242.42  5141.5 2244.39
  5159.6 2246.95  5169.9 2247.22  5177.6 2248.80  5182.8 2249.50  5200.8 2250.94
#Mann=3,-1,0
  4894.7    0.07       0  5009.9    0.05       0  5015.6    0.07       0
Bank Sta=5009.9,5015.6
Exp/Cntr=0.3,0.1

Type RM Length L Ch R = 1,1462,484,484,484
BEGIN DESCRIPTION:
Stream0219 3.0
END DESCRIPTION:
XS GIS Cut Line= 3
      1785175.01     13891024.97      1785225.00     13890875.00
      1785175.01     13890675.03
#Sta/Elev= 30
  4842.0 2256.43  4844.6 2256.43  4863.0 2254.30  4884.1 2251.43  4905.2 2247.16
  4947.4 2241.02  4957.9 2238.27  4968.5 2236.30  4979.0 2233.49  4989.5 2232.29
  4997.4 2230.25  5007.5 2230.21  5007.9 2229.71  5012.8 2229.71  5013.3 2230.21
  5018.1 2231.15  5031.0 2232.43  5041.3 2232.51  5064.5 2233.85  5082.5 2235.37
  5100.6 2237.96  5105.7 2238.21  5123.8 2241.38  5141.8 2245.44  5165.0 2249.28
  5175.3 2250.07  5183.0 2251.09  5188.2 2251.30  5195.9 2252.33  5206.2 2252.89
#Mann=3,-1,0
  4842.0    0.07       0  5007.5    0.05       0  5013.3    0.07       0
Bank Sta=5007.5,5013.3
Exp/Cntr=0.3,0.1

Type RM Length L Ch R = 1,978,444,444,444
BEGIN DESCRIPTION:
Stream0219 2.0
END DESCRIPTION:
XS GIS Cut Line= 3
      1785274.96     13891225.03      1785675.00     13890875.00
      1785825.01     13890724.99
#Sta/Elev= 30
  4468.2 2269.20  4471.6 2269.20  4475.4 2268.21  4532.3 2264.29  4574.5 2260.23
  4595.9 2257.26  4631.0 2253.59  4638.6 2252.32  4645.3 2250.33  4680.9 2245.10
  4716.4 2241.62  4794.3 2236.56  4822.7 2235.53  4929.0 2234.63  4978.4 2230.20
  4986.0 2230.09  4996.4 2228.64  5010.9 2228.02  5011.4 2227.52  5016.3 2227.52
  5016.8 2228.02  5028.0 2229.88  5042.2 2234.57  5056.3 2237.89  5098.7 2243.68
  5127.0 2249.15  5155.3 2253.77  5169.5 2255.06  5208.4 2260.38  5211.9 2260.38
#Mann=3,-1,0
  4468.2    0.07       0  5010.9    0.05       0  5016.8    0.07       0
Bank Sta=5010.9,5016.8
Exp/Cntr=0.3,0.1

Type RM Length L Ch R = 1,534,196,196,196
BEGIN DESCRIPTION:
Stream0219 1.0
END DESCRIPTION:
XS GIS Cut Line= 3
      1785624.96     13891325.02      1786025.00     13891125.00
      1786075.02     13891024.96
#Sta/Elev= 30
  4556.9 2244.48  4570.9 2243.13  4587.7 2239.89  4593.3 2239.93  4610.0 2237.79
  4615.6 2237.90  4632.4 2236.43  4646.4 2236.56  4677.1 2235.29  4811.3 2231.54
  4833.7 2231.77  4839.2 2232.22  4884.0 2231.83  4928.7 2228.76  4945.5 2226.77
  4970.5 2225.79  4971.0 2225.29  4975.9 2225.29  4976.4 2225.79  4995.8 2226.67
  5001.4 2229.52  5007.0 2229.52  5018.1 2234.36  5026.5 2237.12  5034.9 2238.76
  5062.9 2241.64  5079.6 2243.97  5085.2 2244.18  5113.2 2247.87  5116.0 2247.87
#Mann=3,-1,0
  4556.9    0.07       0  4970.5    0.05       0  4976.4    0.07       0
Bank Sta=4970.5,4976.4
Exp/Cntr=0.3,0.1

Type RM Length L Ch R = 1,338,205,205,205
BEGIN DESCRIPTION:
Stream0219 0.0
END DESCRIPTION:
XS GIS Cut Line= 5
      1785557.69     13891403.67      1785715.22     13891409.22
      1785979.88     13891402.49      1786184.52     13891225.87
      1786245.90     13891096.15
#Sta/Elev= 30
  4419.8 2251.15  4427.1 2250.09  4467.1 2247.20  4497.2 2242.63  4507.2 2241.60
  4527.2 2238.05  4547.2 2235.07  4567.2 2234.33  4817.3 2232.83  4886.9 2229.77
  4907.8 2229.28  4922.0 2227.92  4942.9 2227.10  4971.4 2225.31  4990.4 2225.10
  4990.8 2224.60  4995.8 2224.60  4996.3 2225.10  4999.9 2225.49  5007.4 2225.32
  5014.2 2226.40  5020.8 2226.92  5049.3 2231.93  5071.2 2233.86  5127.7 2237.41
  5157.7 2240.34  5173.2 2241.08  5195.9 2242.90  5218.7 2246.04  5256.0 2248.31
#Mann=3,-1,0
  4419.8    0.07       0  4990.4    0.05       0  4996.3    0.07       0
Bank Sta=4990.4,4996.3
Exp/Cntr=0.3,0.1

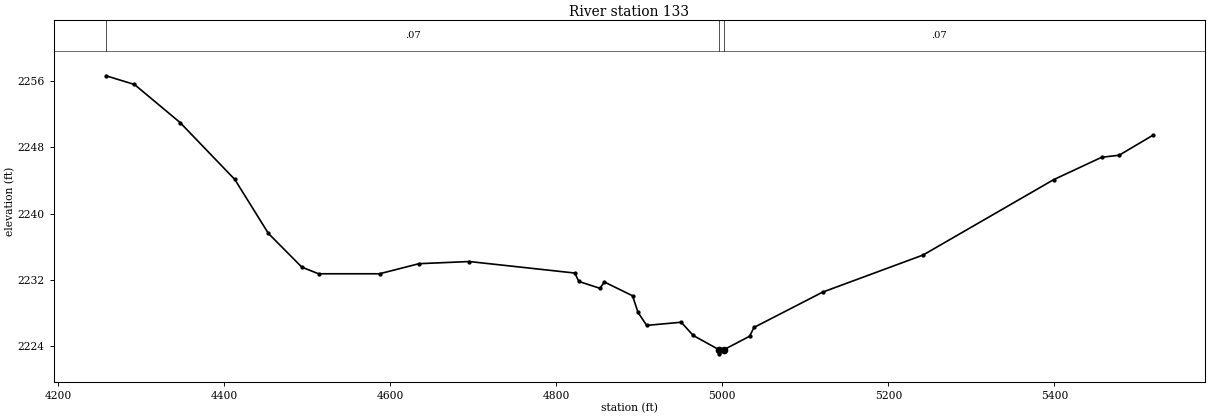
Type RM Length L Ch R = 1,133,0,0,0
BEGIN DESCRIPTION:
Stream0219 0.1
END DESCRIPTION:
XS GIS Cut Line= 4
      1785450.99     13891448.83      1786032.57     13891522.61
      1786247.42     13891461.85      1786515.47     13891098.67
#Sta/Elev= 30
  4257.9 2256.66  4292.2 2255.61  4347.1 2251.01  4413.1 2244.12  4453.5 2237.60
  4493.8 2233.52  4513.9 2232.72  4587.3 2232.72  4634.9 2233.94  4695.4 2234.20
  4822.4 2232.81  4827.4 2231.79  4852.8 2230.96  4858.0 2231.73  4892.0 2230.06
  4898.6 2228.05  4909.0 2226.48  4950.6 2226.86  4965.1 2225.26  4996.1 2223.54
  4996.5 2223.04  5002.0 2223.54  5033.0 2225.17  5038.2 2226.23  5120.9 2230.50
  5241.9 2234.99  5399.1 2244.10  5457.0 2246.81  5477.9 2247.05  5518.8 2249.48
#Mann=3,-1,0
  4257.9    0.07       0  4996.1    0.05       0  5002.0    0.07       0
Bank Sta=4996.1,5002
Exp/Cntr=0.3,0.1

Chan Stop Cuts=-1