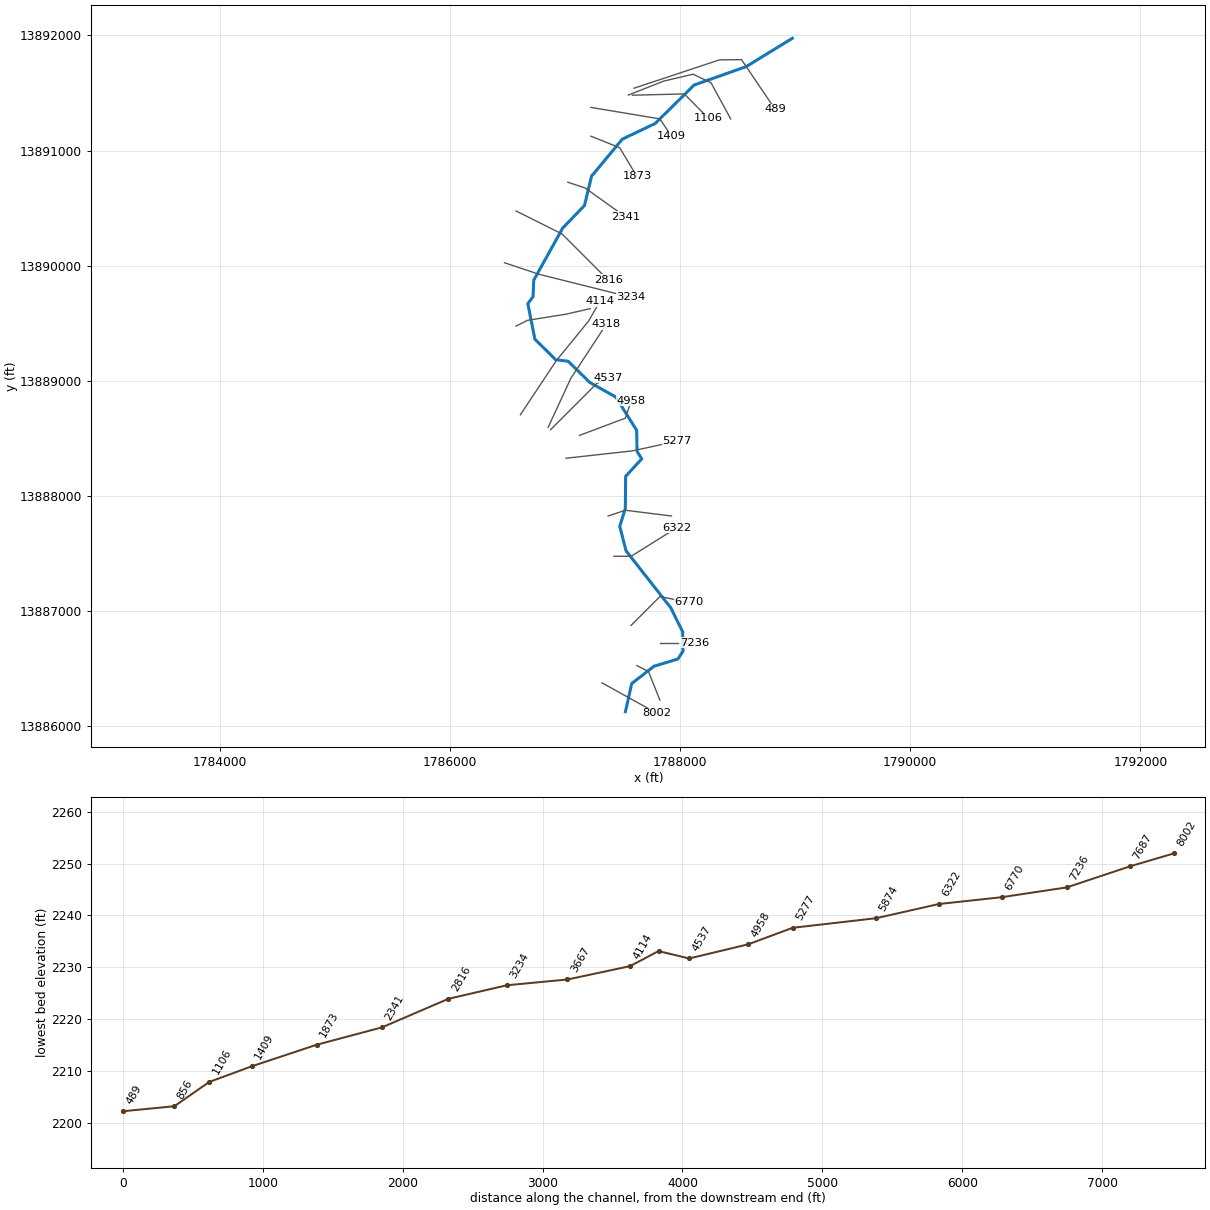
--- Stream0221.prj (project) ---

Proj Title=Stream0221 Base Level Engineering
Current Plan=p01
Default Exp/Contr=0.3,0.1
English Units
Geom File=g01
Flow File=f01
Plan File=p01
BEGIN DESCRIPTION:
Stream0221
END DESCRIPTION:

--- Stream0221.p01 (plan) ---

Plan Title=Multiple Run
Short Identifier=Multiple
Geom File=g01
Flow File=f01
Subcritical Flow
K Sum by GR= 0
Std Step Tol= 0.01
Critical Tol= 0.01
Num of Std Step Trials= 20
Max Error Tol= 0.3
Flow Tol Ratio= 0.001
Split Flow NTrial= 30
Split Flow Tol= 0.02
Split Flow Ratio= 0.02
Log Output Level= 0
Friction Slope Method= 1
Unsteady Friction Slope Method= 2
Unsteady Bridges Friction Slope Method= 1
Parabolic Critical Depth
Global Vel Dist=  1 , 1 , 1
Global Log Level= 0
CheckData=True
Encroach Param= -1, 0, 0, 0
BEGIN DESCRIPTION:
Multiple Run
END DESCRIPTION:

--- Stream0221.f01 (steady flow) ---

Flow Title=Multiple
Number of Profiles=7
Profile Names=10-year,25-year,50-year,1pct_min,100-year,1pct_plu,500-year
River Rch & RM= Stream0221,Reach-1,8002
    1656    2870    4038    2739    5464   10903    9904
Boundary for River Rch & Prof#=Stream0221,Reach-1,1
Up Type=0
Dn Type=3
Dn Slope=0.005
Boundary for River Rch & Prof#=Stream0221,Reach-1,2
Up Type=0
Dn Type=3
Dn Slope=0.005
Boundary for River Rch & Prof#=Stream0221,Reach-1,3
Up Type=0
Dn Type=3
Dn Slope=0.005
Boundary for River Rch & Prof#=Stream0221,Reach-1,4
Up Type=0
Dn Type=3
Dn Slope=0.005
Boundary for River Rch & Prof#=Stream0221,Reach-1,5
Up Type=0
Dn Type=3
Dn Slope=0.005
Boundary for River Rch & Prof#=Stream0221,Reach-1,6
Up Type=0
Dn Type=3
Dn Slope=0.005
Boundary for River Rch & Prof#=Stream0221,Reach-1,7
Up Type=0
Dn Type=3
Dn Slope=0.005

--- Stream0221.g01 (geometry) ---

Geom Title=Existing Conditions

River Reach=Stream0221,Reach-1
Reach XY= 30
      1787525.00     13886125.00      1787580.26     13886369.53
      1787772.70     13886519.17      1787981.50     13886582.72
      1788025.34     13886649.78      1788022.76     13886819.07
      1787919.15     13887027.29      1787530.47     13887522.55
      1787476.10     13887735.55      1787524.48     13887890.22
      1787527.06     13888169.15      1787667.21     13888321.58
      1787626.39     13888385.43      1787622.93     13888569.14
      1787441.71     13888858.36      1787215.32     13888985.78
      1787027.43     13889169.48      1786918.83     13889182.86
      1786738.40     13889361.70      1786677.25     13889669.06
      1786722.73     13889730.94      1786728.76     13889873.44
      1786980.83     13890327.30      1787169.53     13890522.55
      1787230.83     13890777.30      1787497.86     13891098.84
      1787784.68     13891235.76      1788122.57     13891569.48
      1788573.42     13891728.83      1788975.00     13891975.00

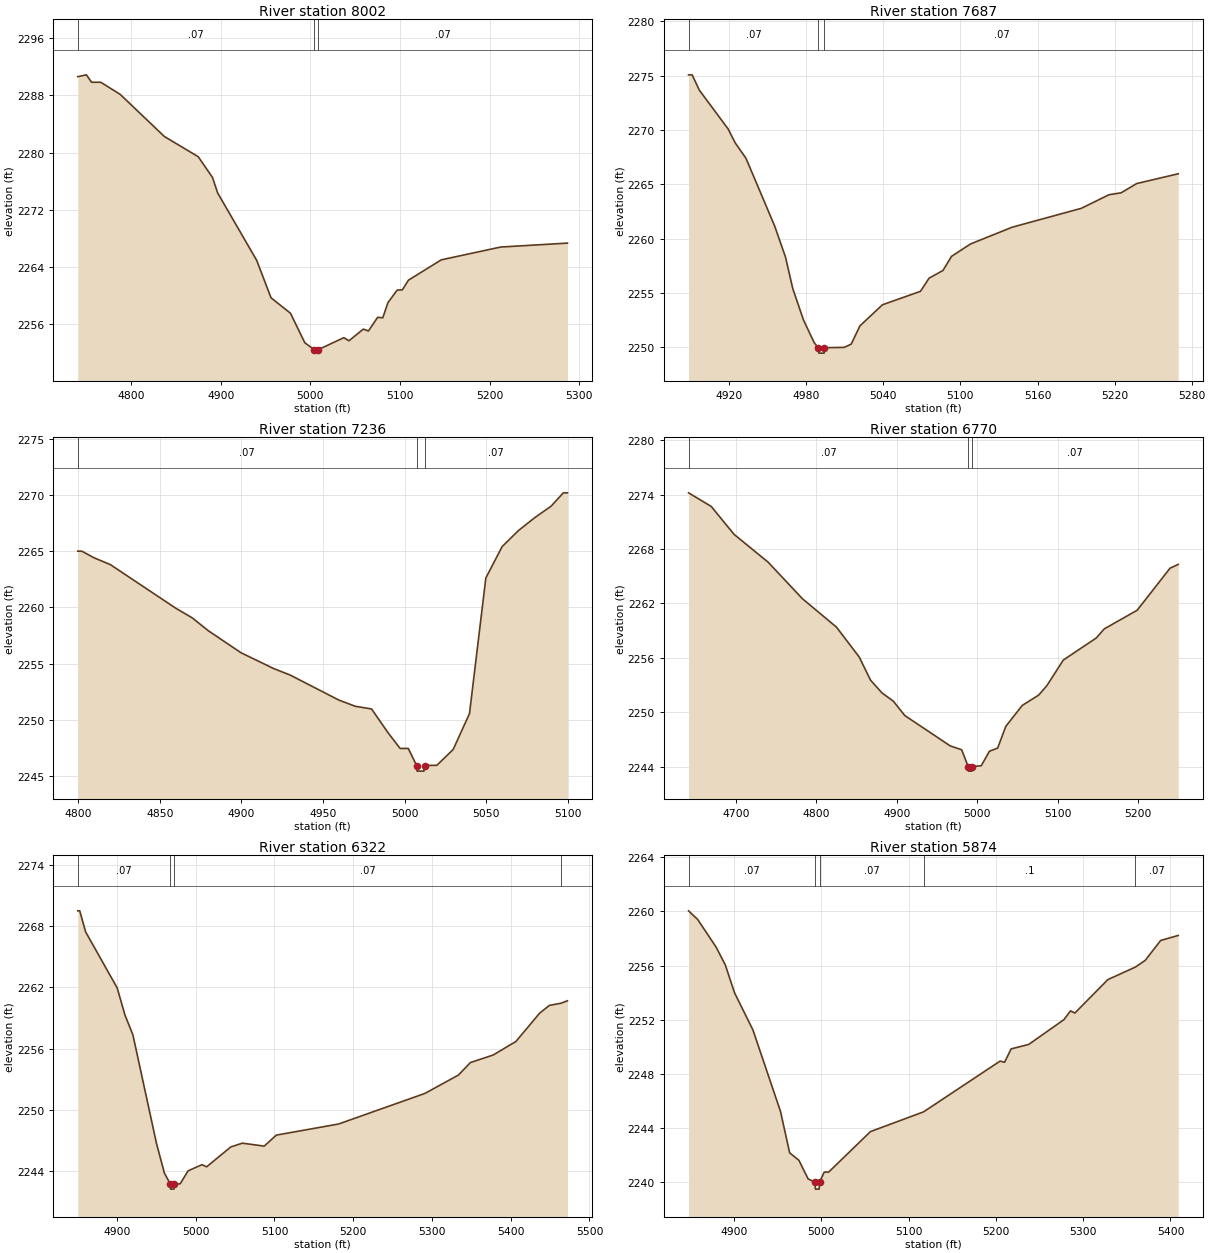
Type RM Length L Ch R = 1,8002,315,315,315
BEGIN DESCRIPTION:
Stream0221 17.0
END DESCRIPTION:
XS GIS Cut Line= 2
      1787322.22     13886375.03      1787800.19     13886110.07
#Sta/Elev= 30
  4740.4 2290.63  4750.0 2290.89  4755.8 2289.85  4766.1 2289.85  4787.8 2288.15
  4837.0 2282.27  4874.8 2279.44  4890.8 2276.53  4896.5 2274.37  4940.0 2264.96
  4956.1 2259.70  4977.8 2257.54  4993.8 2253.41  5004.2 2252.46  5004.5 2251.96
  5008.6 2251.96  5009.0 2252.46  5037.3 2254.12  5043.1 2253.69  5059.1 2255.32
  5064.8 2255.06  5075.1 2256.97  5080.8 2256.90  5086.6 2259.03  5096.9 2260.78
  5102.6 2260.81  5109.5 2262.17  5146.1 2265.01  5212.4 2266.80  5286.9 2267.35
#Mann=3,-1,0
  4740.4    0.07       0  5004.2    0.05       0  5009.0    0.07       0
Bank Sta=5004.2,5009
Exp/Cntr=0.3,0.1

Type RM Length L Ch R = 1,7687,451,451,451
BEGIN DESCRIPTION:
Stream0221 16.0
END DESCRIPTION:
XS GIS Cut Line= 3
      1787624.98     13886525.01      1787725.00     13886475.00
      1787825.01     13886224.98
#Sta/Elev= 30
  4888.4 2275.08  4891.2 2275.08  4896.8 2273.67  4919.2 2270.10  4924.8 2268.80
  4933.1 2267.40  4955.5 2261.14  4963.9 2258.29  4969.5 2255.41  4977.9 2252.50
  4986.2 2250.42  4989.4 2249.96  4989.8 2249.46  4993.9 2249.46  4994.2 2249.96
  5009.6 2249.99  5015.0 2250.29  5021.8 2251.97  5039.3 2253.91  5068.9 2255.15
  5075.6 2256.36  5086.4 2257.07  5093.1 2258.37  5107.9 2259.51  5140.2 2261.05
  5194.1 2262.79  5215.6 2264.04  5225.1 2264.22  5237.2 2265.07  5269.5 2265.97
#Mann=3,-1,0
  4888.4    0.07       0  4989.4    0.05       0  4994.2    0.07       0
Bank Sta=4989.4,4994.2
Exp/Cntr=0.3,0.1

Type RM Length L Ch R = 1,7236,466,466,466
BEGIN DESCRIPTION:
Stream0221 15.0
END DESCRIPTION:
XS GIS Cut Line= 3
      1787824.96     13886725.00      1788025.00     13886725.00
      1788124.96     13886725.00
#Sta/Elev= 30
  4799.8 2265.01  4802.3 2265.01  4809.8 2264.42  4819.8 2263.81  4859.8 2259.93
  4869.8 2259.08  4879.8 2257.92  4899.8 2255.96  4919.8 2254.55  4929.8 2253.98
  4959.8 2251.74  4969.8 2251.19  4979.8 2250.95  4989.8 2248.85  4997.3 2247.43
  5002.3 2247.43  5007.4 2245.91  5007.7 2245.41  5011.9 2245.41  5012.3 2245.91
  5019.8 2245.93  5029.8 2247.34  5039.8 2250.54  5049.8 2262.62  5059.8 2265.42
  5069.8 2266.85  5079.8 2268.00  5089.8 2269.02  5097.3 2270.21  5099.8 2270.21
#Mann=3,-1,0
  4799.8    0.07       0  5007.4    0.05       0  5012.3    0.07       0
Bank Sta=5007.4,5012.3
Exp/Cntr=0.3,0.1

Type RM Length L Ch R = 1,6770,448,448,448
BEGIN DESCRIPTION:
Stream0221 14.0
END DESCRIPTION:
XS GIS Cut Line= 3
      1787575.03     13886875.03      1787825.00     13887125.00
      1788075.04     13887074.99
#Sta/Elev= 30
  4641.1 2274.19  4669.3 2272.69  4697.6 2269.62  4740.1 2266.54  4782.5 2262.53
  4824.9 2259.39  4853.2 2256.10  4867.3 2253.54  4881.5 2252.14  4895.6 2251.23
  4909.8 2249.65  4966.3 2246.30  4980.5 2245.88  4988.6 2244.02  4989.0 2243.52
  4993.2 2243.52  4993.5 2244.02  5004.8 2244.11  5015.0 2245.71  5025.2 2246.06
  5035.4 2248.46  5055.8 2250.76  5076.2 2251.90  5086.4 2252.94  5106.8 2255.76
  5147.6 2258.18  5157.8 2259.20  5198.6 2261.25  5239.4 2265.88  5249.6 2266.30
#Mann=3,-1,0
  4641.1    0.07       0  4988.6    0.05       0  4993.5    0.07       0
Bank Sta=4988.6,4993.5
Exp/Cntr=0.3,0.1

Type RM Length L Ch R = 1,6322,448,448,448
BEGIN DESCRIPTION:
Stream0221 13.0
END DESCRIPTION:
XS GIS Cut Line= 3
      1787424.95     13887475.00      1787575.00     13887475.00
      1787974.96     13887724.97
#Sta/Elev= 30
  4850.3 2269.52  4852.8 2269.52  4860.3 2267.45  4900.3 2261.96  4910.3 2259.28
  4920.3 2257.35  4950.3 2246.68  4960.3 2243.78  4967.8 2242.71  4968.2 2242.21
  4972.5 2242.21  4972.8 2242.71  4980.3 2242.73  4990.3 2244.00  5008.0 2244.61
  5013.9 2244.40  5044.6 2246.35  5059.3 2246.72  5087.0 2246.43  5102.4 2247.51
  5181.4 2248.60  5291.0 2251.60  5333.5 2253.40  5348.8 2254.63  5377.7 2255.37
  5406.6 2256.70  5436.7 2259.48  5449.1 2260.24  5463.6 2260.45  5472.0 2260.69
#Mann=4,-1,0
  4850.3    0.07       0  4967.8    0.05       0  4972.8    0.07       0
  5463.6     0.1       0
Bank Sta=4967.8,4972.8
Exp/Cntr=0.3,0.1

Type RM Length L Ch R = 1,5874,597,597,597
BEGIN DESCRIPTION:
Stream0221 12.0
END DESCRIPTION:
XS GIS Cut Line= 3
      1787375.02     13887825.01      1787525.00     13887875.00
      1787924.99     13887825.00
#Sta/Elev= 30
  4847.7 2260.04  4858.2 2259.40  4879.3 2257.36  4889.8 2256.05  4900.4 2253.99
  4921.5 2251.24  4953.1 2245.22  4963.6 2242.16  4974.2 2241.61  4984.7 2240.24
  4992.7 2239.98  4993.1 2239.48  4997.4 2239.48  4997.8 2239.98  5003.2 2240.74
  5008.3 2240.74  5056.2 2243.73  5117.1 2245.19  5204.8 2248.94  5209.9 2248.85
  5217.4 2249.84  5237.6 2250.17  5277.9 2252.00  5285.5 2252.65  5290.5 2252.49
  5328.3 2254.96  5359.7 2255.88  5371.1 2256.38  5388.8 2257.85  5408.9 2258.22
#Mann=5,-1,0
  4847.7    0.07       0  4992.7    0.05       0  4997.8    0.07       0
  5117.1     0.1       0  5359.7    0.07       0
Bank Sta=4992.7,4997.8
Exp/Cntr=0.3,0.1

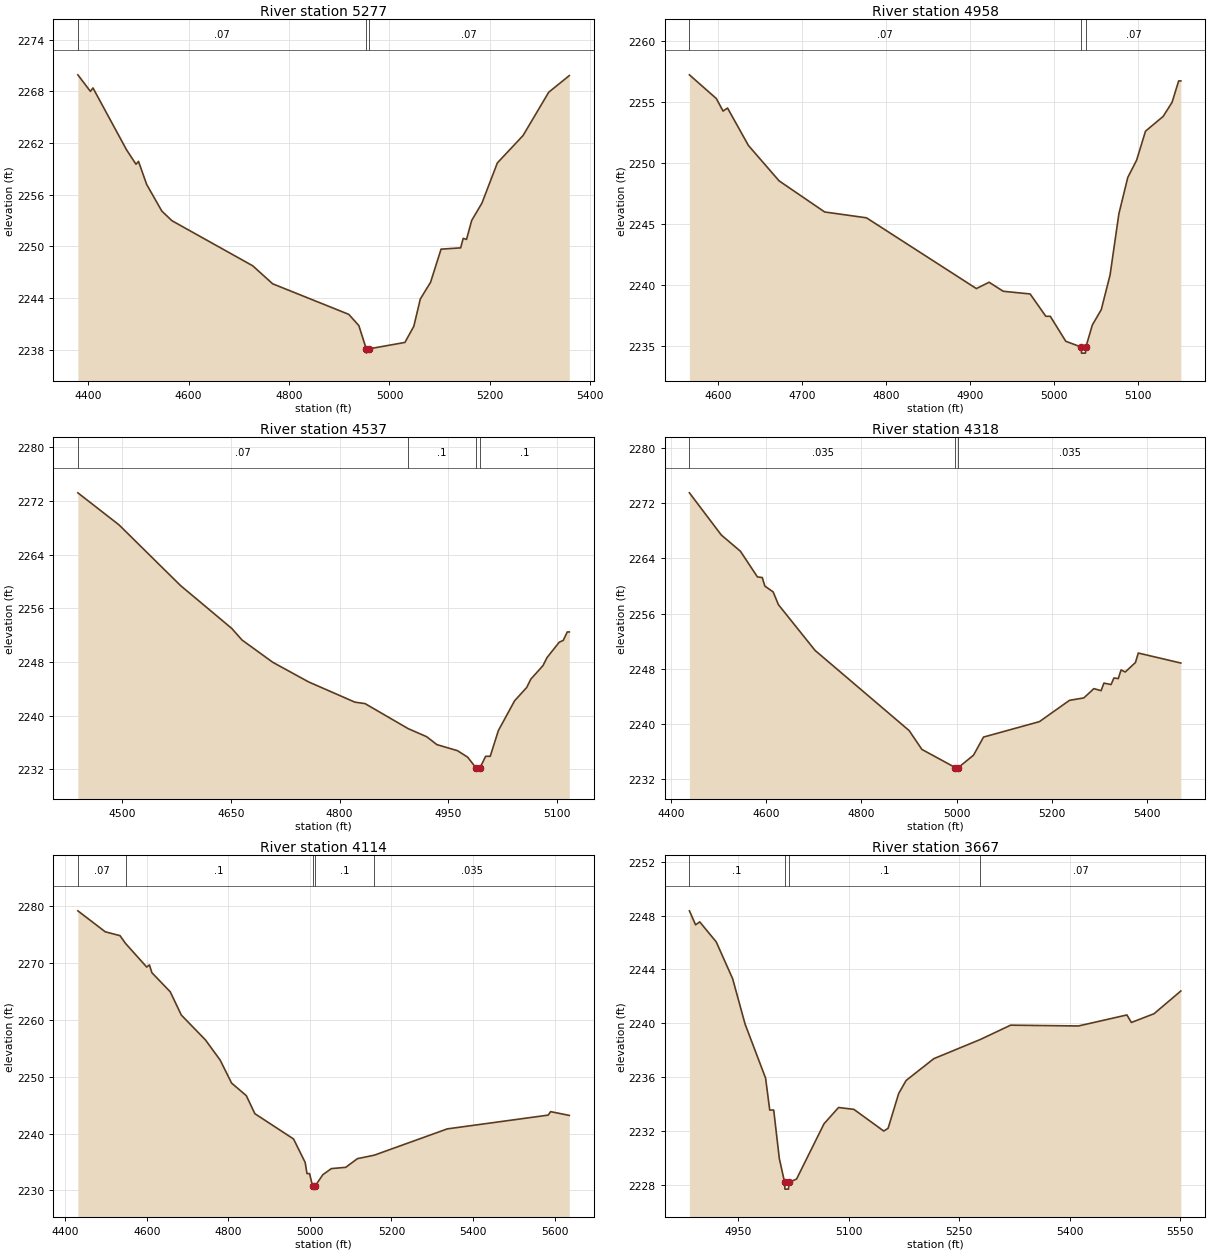
Type RM Length L Ch R = 1,5277,319,319,319
BEGIN DESCRIPTION:
Stream0221 11.0
END DESCRIPTION:
XS GIS Cut Line= 3
      1787008.78     13888326.84      1787584.92     13888390.58
      1787975.03     13888475.01
#Sta/Elev= 30
  4379.4 2269.91  4404.4 2267.99  4409.5 2268.39  4476.2 2261.23  4495.2 2259.54
  4500.2 2259.87  4516.5 2257.19  4546.6 2254.11  4566.8 2252.99  4727.7 2247.76
  4767.4 2245.67  4918.9 2242.13  4939.0 2240.83  4953.8 2238.13  4954.2 2237.63
  4959.4 2238.13  5030.8 2238.87  5048.5 2240.74  5061.5 2243.91  5081.9 2245.85
  5102.8 2249.69  5141.8 2249.84  5146.9 2250.94  5153.5 2250.82  5163.8 2253.02
  5184.2 2255.03  5214.9 2259.69  5266.1 2262.87  5317.2 2267.89  5358.2 2269.82
#Mann=3,-1,0
  4379.4    0.07       0  4953.8    0.05       0  4959.4    0.07       0
Bank Sta=4953.8,4959.4
Exp/Cntr=0.3,0.1

Type RM Length L Ch R = 1,4958,421,421,421
BEGIN DESCRIPTION:
Stream0221 10.0
END DESCRIPTION:
XS GIS Cut Line= 3
      1787124.99     13888525.00      1787525.00     13888675.00
      1787574.99     13888824.98
#Sta/Elev= 30
  4566.2 2257.25  4598.2 2255.31  4606.3 2254.28  4611.6 2254.53  4636.5 2251.46
  4673.0 2248.56  4727.3 2246.01  4777.1 2245.53  4908.0 2239.73  4923.1 2240.25
  4940.0 2239.51  4972.0 2239.29  4990.7 2237.46  4996.0 2237.46  5014.5 2235.41
  5032.8 2234.94  5033.2 2234.44  5037.9 2234.44  5038.4 2234.94  5046.1 2236.75
  5056.7 2238.00  5067.2 2240.84  5077.7 2245.86  5088.3 2248.84  5098.8 2250.25
  5109.4 2252.63  5130.4 2253.84  5141.0 2254.99  5148.9 2256.75  5151.5 2256.75
#Mann=3,-1,0
  4566.2    0.07       0  5032.8    0.05       0  5038.4    0.07       0
Bank Sta=5032.8,5038.4
Exp/Cntr=0.3,0.1

Type RM Length L Ch R = 1,4537,219,219,219
BEGIN DESCRIPTION:
Stream0221 9.0
END DESCRIPTION:
XS GIS Cut Line= 3
      1786874.97     13888574.97      1787275.00     13888975.00
      1787374.98     13889024.99
#Sta/Elev= 30
  4439.1 2273.19  4495.7 2268.43  4580.6 2259.38  4651.3 2252.98  4665.4 2251.26
  4707.8 2247.94  4757.3 2245.01  4821.0 2242.00  4835.1 2241.78  4894.5 2238.05
  4920.0 2236.85  4934.1 2235.67  4962.4 2234.77  4976.5 2233.80  4987.9 2232.22
  4988.3 2231.72  4993.0 2231.72  4993.5 2232.22  5001.3 2233.93  5007.6 2233.93
  5018.8 2237.76  5041.2 2242.20  5057.9 2244.19  5063.5 2245.42  5080.3 2247.44
  5085.9 2248.64  5102.7 2250.93  5108.2 2251.20  5113.8 2252.46  5116.6 2252.46
#Mann=4,-1,0
  4439.1    0.07       0  4894.5     0.1       0  4987.9    0.05       0
  4993.5     0.1       0
Bank Sta=4987.9,4993.5
Exp/Cntr=0.3,0.1

Type RM Length L Ch R = 1,4318,204,204,204
BEGIN DESCRIPTION:
Stream0221 8.2
END DESCRIPTION:
XS GIS Cut Line= 3
      1786853.71     13888595.13      1787050.81     13889020.91
      1787360.39     13889492.85
#Sta/Elev= 30
  4438.1 2273.51  4505.1 2267.40  4545.5 2265.03  4581.2 2261.31  4591.3 2261.22
  4596.8 2259.98  4614.2 2259.14  4625.3 2257.29  4702.4 2250.65  4900.3 2239.02
  4927.1 2236.29  4997.7 2233.64  4998.2 2233.14  5003.4 2233.64  5035.6 2235.45
  5056.7 2238.08  5174.3 2240.32  5237.5 2243.41  5267.7 2243.76  5288.8 2245.11
  5303.9 2244.81  5309.9 2245.91  5325.0 2245.70  5330.9 2246.65  5340.1 2246.57
  5346.0 2247.82  5354.7 2247.52  5376.2 2248.89  5382.2 2250.27  5471.7 2248.82
#Mann=3,-1,0
  4438.1   0.035       0  4997.7   0.035       0  5003.4   0.035       0
Bank Sta=4997.7,5003.4
Exp/Cntr=0.3,0.1

Type RM Length L Ch R = 1,4114,447,447,447
BEGIN DESCRIPTION:
Stream0221 8.0
END DESCRIPTION:
XS GIS Cut Line= 4
      1786612.56     13888704.34      1786925.00     13889175.00
      1787206.36     13889520.18      1787303.16     13889689.28
#Sta/Elev= 30
  4430.9 2279.16  4498.2 2275.47  4534.2 2274.80  4547.8 2273.43  4599.7 2269.28
  4606.4 2269.65  4612.4 2268.29  4657.5 2264.92  4684.6 2260.84  4743.8 2256.47
  4779.8 2252.93  4807.9 2248.88  4844.0 2246.67  4865.0 2243.50  4959.8 2239.06
  4988.3 2234.93  4992.8 2232.97  4999.1 2232.97  5006.6 2230.74  5007.1 2230.24
  5012.3 2230.74  5031.7 2232.78  5052.6 2233.85  5087.7 2234.07  5116.5 2235.60
  5157.9 2236.21  5336.9 2240.83  5584.3 2243.25  5590.1 2243.86  5636.0 2243.20
#Mann=5,-1,0
  4430.9    0.07       0  4547.8     0.1       0  5006.6    0.05       0
  5012.3     0.1       0  5157.9   0.035       0
Bank Sta=5006.6,5012.3
Exp/Cntr=0.3,0.1

Type RM Length L Ch R = 1,3667,433,433,433
BEGIN DESCRIPTION:
Stream0221 7.0
END DESCRIPTION:
XS GIS Cut Line= 4
      1786574.98     13889474.99      1786675.00     13889525.00
      1787004.51     13889577.62      1787220.47     13889626.33
#Sta/Elev= 30
  4883.9 2248.36  4892.3 2247.32  4897.9 2247.54  4920.3 2246.05  4942.6 2243.31
  4959.4 2239.95  4987.3 2235.92  4992.9 2233.55  4998.3 2233.55  5005.9 2229.95
  5013.1 2228.17  5013.5 2227.67  5018.4 2227.67  5018.9 2228.17  5029.3 2228.42
  5066.6 2232.53  5086.3 2233.74  5107.1 2233.60  5147.6 2231.99  5153.5 2232.19
  5167.9 2234.78  5178.0 2235.75  5215.6 2237.37  5278.9 2238.80  5319.8 2239.86
  5411.9 2239.80  5477.6 2240.62  5483.7 2240.06  5514.4 2240.71  5550.8 2242.40
#Mann=4,-1,0
  4883.9     0.1       0  5013.1    0.05       0  5018.9     0.1       0
  5278.9    0.07       0
Bank Sta=5013.1,5018.9
Exp/Cntr=0.3,0.1

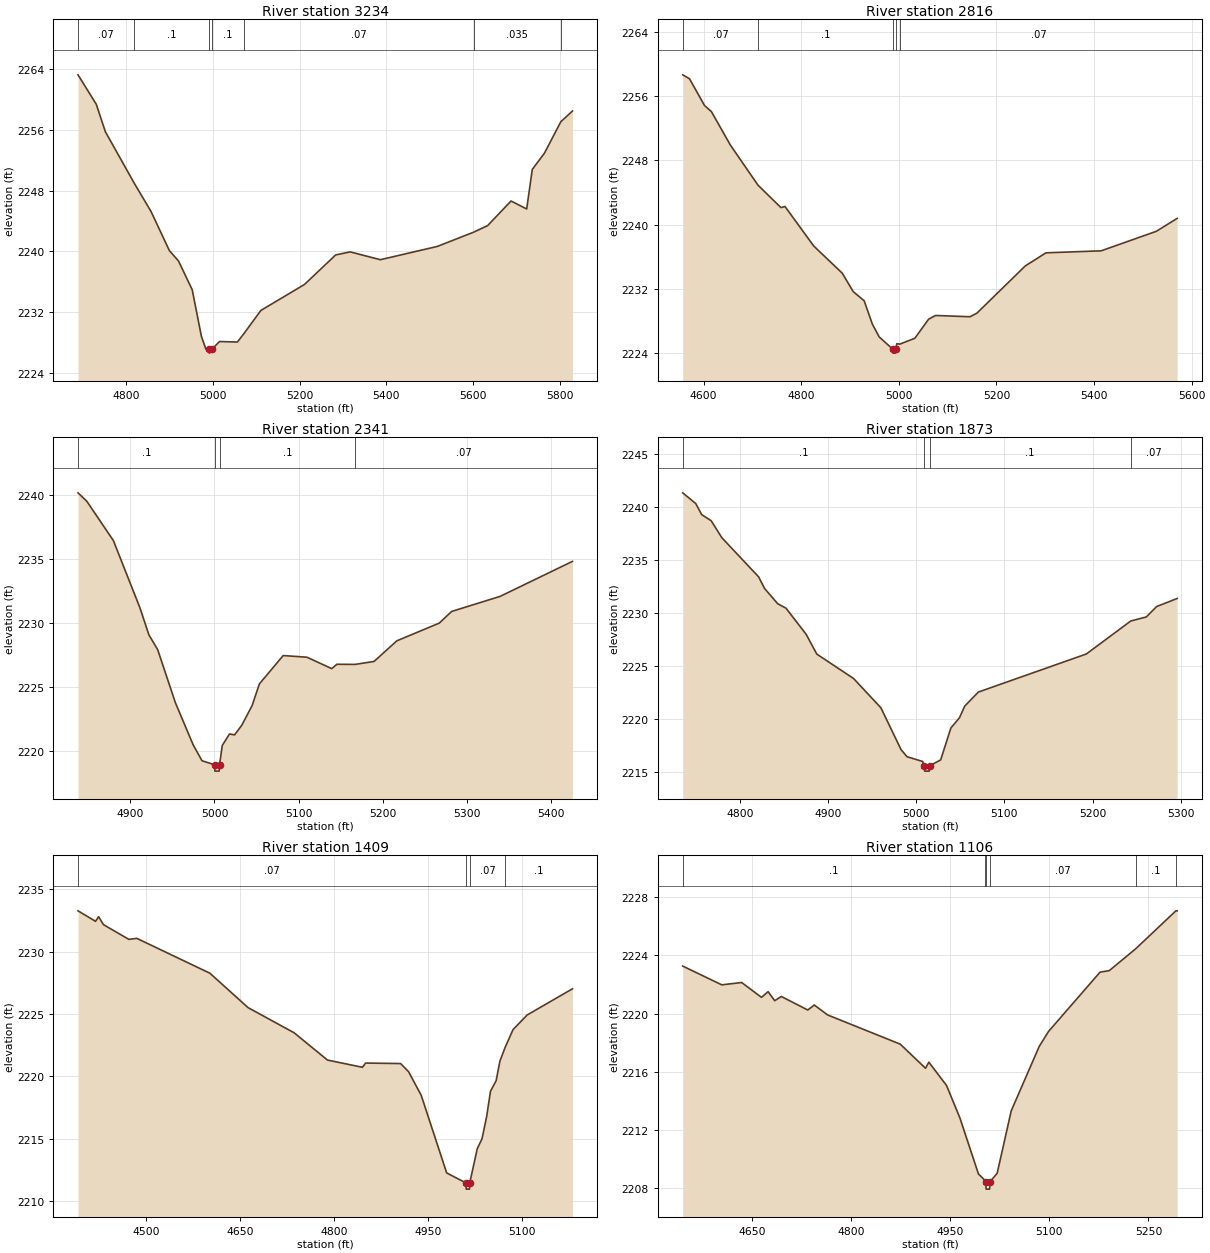
Type RM Length L Ch R = 1,3234,418,418,418
BEGIN DESCRIPTION:
Stream0221 6.0
END DESCRIPTION:
XS GIS Cut Line= 3
      1786475.03     13890024.99      1786775.00     13889925.00
      1787574.98     13889725.01
#Sta/Elev= 30
  4688.4 2263.26  4730.5 2259.38  4751.6 2255.75  4818.4 2248.94  4857.0 2245.23
  4899.2 2240.08  4920.3 2238.71  4951.9 2234.92  4973.0 2228.80  4983.5 2227.08
  4991.1 2227.06  4991.6 2226.56  4997.0 2227.06  5014.9 2228.09  5056.1 2228.02
  5071.4 2229.15  5110.3 2232.19  5210.8 2235.61  5282.9 2239.51  5316.4 2239.91
  5386.0 2238.88  5517.4 2240.63  5601.2 2242.51  5633.4 2243.37  5687.5 2246.62
  5723.6 2245.57  5736.5 2250.78  5764.8 2252.95  5802.3 2257.07  5829.2 2258.49
#Mann=7,-1,0
  4688.4    0.07       0  4818.4     0.1       0  4991.1    0.05       0
  4997.0     0.1       0  5071.4    0.07       0  5601.2   0.035       0
  5802.3    0.07       0
Bank Sta=4991.1,4997
Exp/Cntr=0.3,0.1

Type RM Length L Ch R = 1,2816,475,475,475
BEGIN DESCRIPTION:
Stream0221 5.0
END DESCRIPTION:
XS GIS Cut Line= 3
      1786575.04     13890474.98      1786975.00     13890275.00
      1787375.03     13889874.97
#Sta/Elev= 30
  4557.4 2258.69  4571.3 2258.20  4602.1 2254.86  4616.1 2254.11  4655.2 2249.91
  4711.6 2244.92  4758.6 2242.12  4767.0 2242.25  4825.7 2237.33  4884.4 2233.92
  4906.7 2231.63  4929.1 2230.49  4945.9 2227.58  4959.8 2225.98  4987.6 2224.45
  4988.1 2223.95  4993.0 2223.95  4993.5 2224.45  4996.2 2225.13  5002.0 2225.07
  5032.9 2225.80  5061.1 2228.18  5075.3 2228.65  5146.0 2228.49  5160.1 2228.94
  5259.1 2234.83  5301.6 2236.47  5414.7 2236.72  5527.8 2239.16  5570.3 2240.77
#Mann=5,-1,0
  4557.4    0.07       0  4711.6     0.1       0  4987.6    0.05       0
  4993.5     0.1       0  5002.0    0.07       0
Bank Sta=4987.6,4993.5
Exp/Cntr=0.3,0.1

Type RM Length L Ch R = 1,2341,468,468,468
BEGIN DESCRIPTION:
Stream0221 4.0
END DESCRIPTION:
XS GIS Cut Line= 3
      1787025.04     13890724.99      1787175.00     13890675.00
      1787525.01     13890424.99
#Sta/Elev= 30
  4837.7 2240.17  4848.2 2239.51  4879.8 2236.44  4911.4 2231.19  4922.0 2229.09
  4932.5 2227.93  4953.6 2223.78  4974.7 2220.50  4985.2 2219.26  5000.1 2218.95
  5000.6 2218.45  5005.6 2218.45  5006.1 2218.95  5009.3 2220.45  5017.9 2221.35
  5024.0 2221.28  5032.6 2222.04  5044.9 2223.58  5053.5 2225.26  5081.8 2227.47
  5110.1 2227.34  5139.5 2226.45  5145.7 2226.79  5167.4 2226.78  5189.9 2227.01
  5217.0 2228.62  5267.4 2230.00  5282.1 2230.91  5339.9 2232.09  5425.9 2234.82
#Mann=4,-1,0
  4837.7     0.1       0  5000.1    0.05       0  5006.1     0.1       0
  5167.4    0.07       0
Bank Sta=5000.1,5006.1
Exp/Cntr=0.3,0.1

Type RM Length L Ch R = 1,1873,464,464,464
BEGIN DESCRIPTION:
Stream0221 3.0
END DESCRIPTION:
XS GIS Cut Line= 3
      1787225.03     13891124.99      1787475.00     13891025.00
      1787625.01     13890774.98
#Sta/Elev= 30
  4735.1 2241.32  4749.9 2240.31  4756.6 2239.27  4767.4 2238.69  4779.5 2237.09
  4821.2 2233.40  4828.0 2232.30  4842.8 2230.87  4852.2 2230.45  4875.1 2227.99
  4887.2 2226.12  4928.9 2223.82  4959.9 2221.06  4982.8 2217.11  4989.5 2216.45
  5007.2 2216.00  5009.1 2215.59  5009.6 2215.09  5014.7 2215.09  5015.2 2215.59
  5027.7 2216.15  5039.3 2219.16  5049.0 2220.12  5054.9 2221.21  5070.4 2222.54
  5192.9 2226.13  5243.3 2229.24  5260.9 2229.62  5272.6 2230.60  5295.9 2231.36
#Mann=4,-1,0
  4735.1     0.1       0  5009.1    0.05       0  5015.2     0.1       0
  5243.3    0.07       0
Bank Sta=5009.1,5015.2
Exp/Cntr=0.3,0.1

Type RM Length L Ch R = 1,1409,303,303,303
BEGIN DESCRIPTION:
Stream0221 2.0
END DESCRIPTION:
XS GIS Cut Line= 3
      1787225.00     13891375.00      1787825.00     13891275.00
      1787925.03     13891124.96
#Sta/Elev= 30
  4391.5 2233.28  4419.4 2232.44  4424.4 2232.81  4432.1 2232.17  4472.6 2230.99
  4485.3 2231.07  4601.9 2228.27  4662.7 2225.51  4736.2 2223.49  4789.4 2221.30
  4845.2 2220.72  4850.2 2221.06  4906.0 2221.02  4918.7 2220.37  4938.9 2218.47
  4979.5 2212.24  5010.2 2211.44  5010.7 2210.94  5015.8 2210.94  5016.3 2211.44
  5028.3 2214.19  5035.8 2214.97  5043.3 2216.78  5049.4 2218.80  5058.4 2219.65
  5064.4 2221.21  5072.9 2222.34  5085.4 2223.75  5107.9 2224.92  5180.1 2227.02
#Mann=4,-1,0
  4391.5    0.07       0  5010.2    0.05       0  5016.3    0.07       0
  5072.9     0.1       0
Bank Sta=5010.2,5016.3
Exp/Cntr=0.3,0.1

Type RM Length L Ch R = 1,1106,250,250,250
BEGIN DESCRIPTION:
Stream0221 1.0
END DESCRIPTION:
XS GIS Cut Line= 3
      1787585.87     13891480.91      1788036.54     13891491.97
      1788245.71     13891280.70
#Sta/Elev= 30
  4545.4 2223.27  4604.5 2221.98  4634.6 2222.14  4664.6 2221.12  4674.6 2221.51
  4684.6 2220.89  4694.6 2221.18  4734.6 2220.25  4744.6 2220.59  4764.6 2219.91
  4874.6 2217.90  4912.8 2216.24  4917.8 2216.66  4944.6 2215.06  4964.7 2212.84
  4992.9 2208.97  5002.2 2208.56  5004.0 2208.43  5004.5 2207.93  5009.7 2207.93
  5010.2 2208.43  5021.2 2209.02  5042.5 2213.32  5084.9 2217.75  5099.0 2218.78
  5176.8 2222.85  5190.9 2222.96  5230.8 2224.46  5291.6 2227.07  5293.5 2227.07
#Mann=6,-1,0
  4545.4     0.1       0  5002.2    0.07       0  5004.0    0.05       0
  5010.2    0.07       0  5230.8     0.1       0  5291.6    0.07       0
Bank Sta=5004,5010.2
Exp/Cntr=0.3,0.1

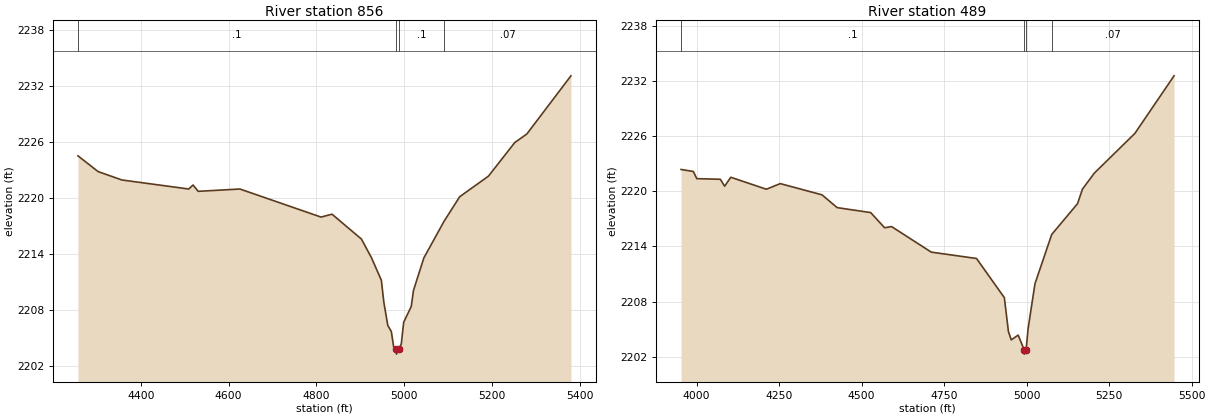
Type RM Length L Ch R = 1,856,367,367,367
BEGIN DESCRIPTION:
Stream0221 0.0
END DESCRIPTION:
XS GIS Cut Line= 5
      1787550.35     13891481.88      1787858.23     13891603.71
      1788112.68     13891663.30      1788269.11     13891588.71
      1788439.80     13891274.98
#Sta/Elev= 30
  4257.0 2224.52  4302.9 2222.83  4357.0 2221.93  4509.4 2220.96  4519.2 2221.39
  4530.9 2220.71  4625.9 2220.96  4810.7 2217.95  4835.7 2218.26  4902.7 2215.59
  4925.4 2213.61  4948.1 2211.17  4953.7 2208.83  4962.8 2206.32  4970.8 2205.68
  4976.3 2203.98  4981.9 2203.75  4982.4 2203.25  4988.1 2203.75  4993.5 2204.36
  4999.0 2206.68  5016.2 2208.36  5021.2 2210.07  5044.8 2213.56  5090.8 2217.49
  5126.5 2220.13  5192.0 2222.34  5251.9 2225.94  5279.4 2226.86  5379.9 2233.10
#Mann=4,-1,0
  4257.0     0.1       0  4981.9    0.05       0  4988.1     0.1       0
  5090.8    0.07       0
Bank Sta=4981.9,4988.1
Exp/Cntr=0.3,0.1

Type RM Length L Ch R = 1,489,0,0,0
BEGIN DESCRIPTION:
Stream0221 0.1
END DESCRIPTION:
XS GIS Cut Line= 4
      1787599.71     13891541.57      1788342.76     13891788.09
      1788533.73     13891789.83      1788825.17     13891359.60
#Sta/Elev= 30
  3953.2 2222.37  3990.4 2222.15  4000.9 2221.37  4072.3 2221.30  4085.2 2220.55
  4104.0 2221.52  4211.6 2220.22  4253.8 2220.83  4380.2 2219.61  4426.1 2218.22
  4527.7 2217.68  4569.9 2216.03  4590.9 2216.16  4711.2 2213.38  4848.3 2212.69
  4932.6 2208.43  4945.0 2204.74  4953.5 2203.84  4974.5 2204.36  4992.4 2202.79
  4992.9 2202.29  4998.6 2202.79  5004.4 2205.02  5025.4 2209.95  5076.1 2215.30
  5154.3 2218.65  5169.2 2220.23  5205.2 2221.97  5328.0 2226.29  5446.7 2232.55
#Mann=4,-1,0
  3953.2     0.1       0  4992.4    0.05       0  4998.6     0.1       0
  5076.1    0.07       0
Bank Sta=4992.4,4998.6
Exp/Cntr=0.3,0.1

Chan Stop Cuts=-1