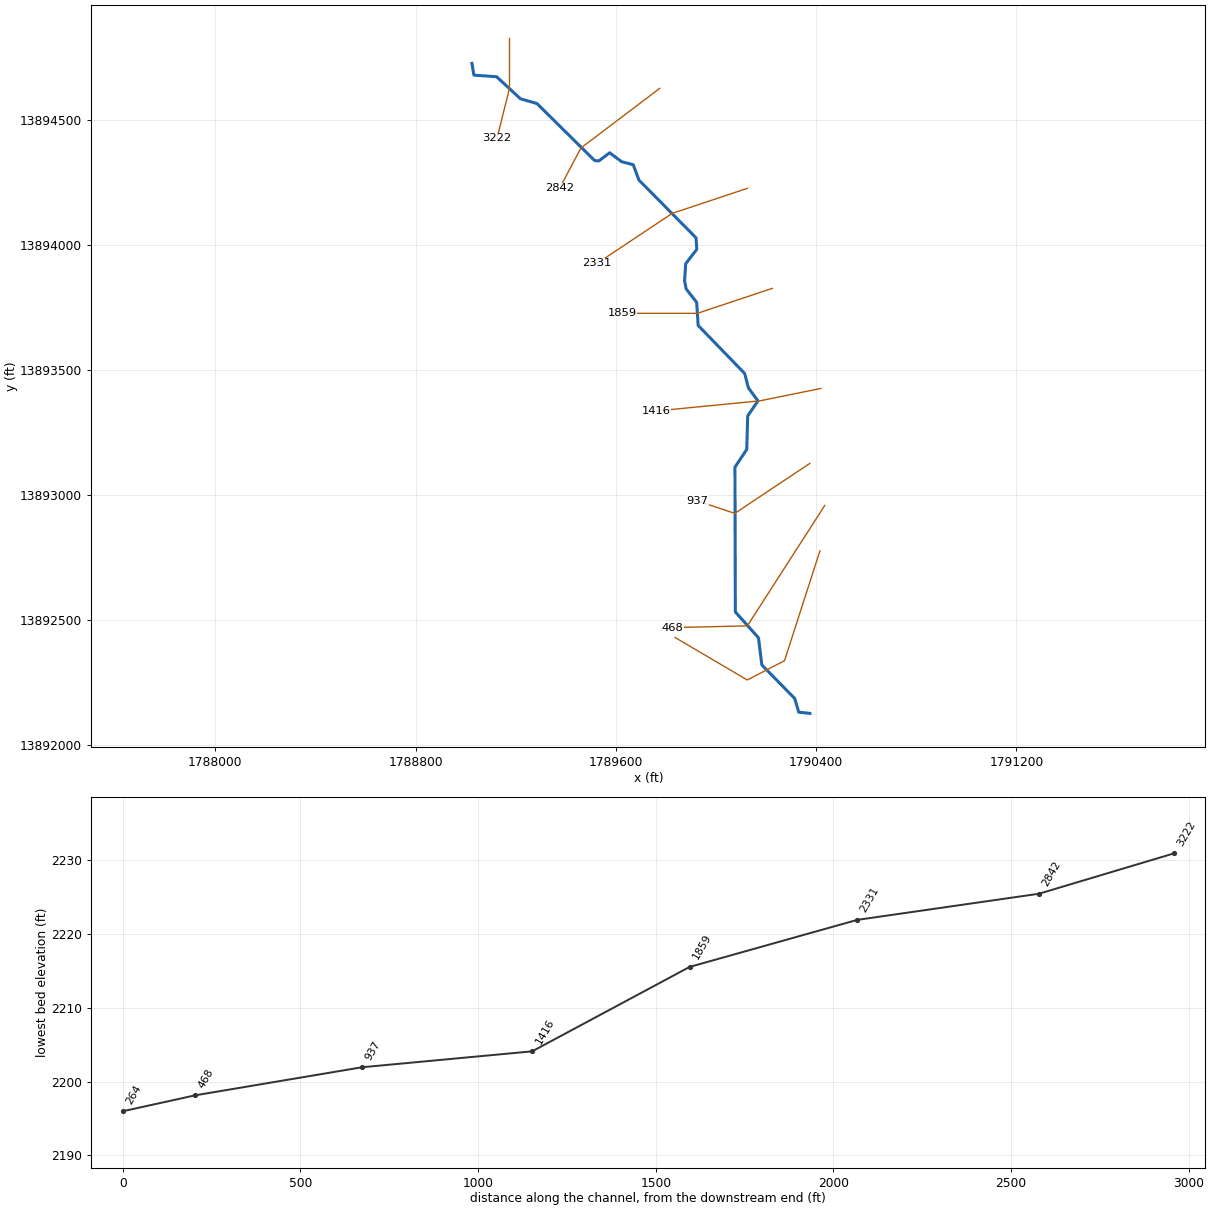
--- Stream0223.prj (project) ---

Proj Title=Stream0223 Base Level Engineering
Current Plan=p01
Default Exp/Contr=0.3,0.1
English Units
Geom File=g01
Flow File=f01
Plan File=p01
BEGIN DESCRIPTION:
Stream0223
END DESCRIPTION:

--- Stream0223.p01 (plan) ---

Plan Title=Multiple Run
Short Identifier=Multiple
Geom File=g01
Flow File=f01
Subcritical Flow
K Sum by GR= 0
Std Step Tol= 0.01
Critical Tol= 0.01
Num of Std Step Trials= 20
Max Error Tol= 0.3
Flow Tol Ratio= 0.001
Split Flow NTrial= 30
Split Flow Tol= 0.02
Split Flow Ratio= 0.02
Log Output Level= 0
Friction Slope Method= 1
Unsteady Friction Slope Method= 2
Unsteady Bridges Friction Slope Method= 1
Parabolic Critical Depth
Global Vel Dist=  1 , 1 , 1
Global Log Level= 0
CheckData=True
Encroach Param= -1, 0, 0, 0
BEGIN DESCRIPTION:
Multiple Run
END DESCRIPTION:

--- Stream0223.f01 (steady flow) ---

Flow Title=Multiple
Number of Profiles=7
Profile Names=10-year,25-year,50-year,1pct_min,100-year,1pct_plu,500-year
River Rch & RM= Stream0223,Reach-1,3222
     894    1507    2082    1391    2775    5536    4872
Boundary for River Rch & Prof#=Stream0223,Reach-1,1
Up Type=0
Dn Type=3
Dn Slope=0.005
Boundary for River Rch & Prof#=Stream0223,Reach-1,2
Up Type=0
Dn Type=3
Dn Slope=0.005
Boundary for River Rch & Prof#=Stream0223,Reach-1,3
Up Type=0
Dn Type=3
Dn Slope=0.005
Boundary for River Rch & Prof#=Stream0223,Reach-1,4
Up Type=0
Dn Type=3
Dn Slope=0.005
Boundary for River Rch & Prof#=Stream0223,Reach-1,5
Up Type=0
Dn Type=3
Dn Slope=0.005
Boundary for River Rch & Prof#=Stream0223,Reach-1,6
Up Type=0
Dn Type=3
Dn Slope=0.005
Boundary for River Rch & Prof#=Stream0223,Reach-1,7
Up Type=0
Dn Type=3
Dn Slope=0.005

--- Stream0223.g01 (geometry) ---

Geom Title=Existing Conditions

River Reach=Stream0223,Reach-1
Reach XY= 30
      1789025.00     13894725.00      1789032.76     13894677.84
      1789123.47     13894671.42      1789218.96     13894583.18
      1789284.68     13894564.22      1789515.00     13894336.24
      1789531.66     13894334.60      1789574.94     13894367.24
      1789623.04     13894331.54      1789669.38     13894319.44
      1789691.73     13894258.52      1789919.91     13894027.30
      1789923.21     13893981.13      1789878.74     13893923.42
      1789874.41     13893854.95      1789880.68     13893822.69
      1789922.64     13893769.02      1789928.61     13893676.50
      1790114.25     13893484.68      1790129.45     13893426.65
      1790167.47     13893375.01      1790126.40     13893314.56
      1790122.73     13893180.94      1790075.52     13893109.78
      1790077.07     13892530.86      1790169.46     13892427.42
      1790182.86     13892318.83      1790314.28     13892184.54
      1790330.33     13892129.92      1790375.00     13892125.00

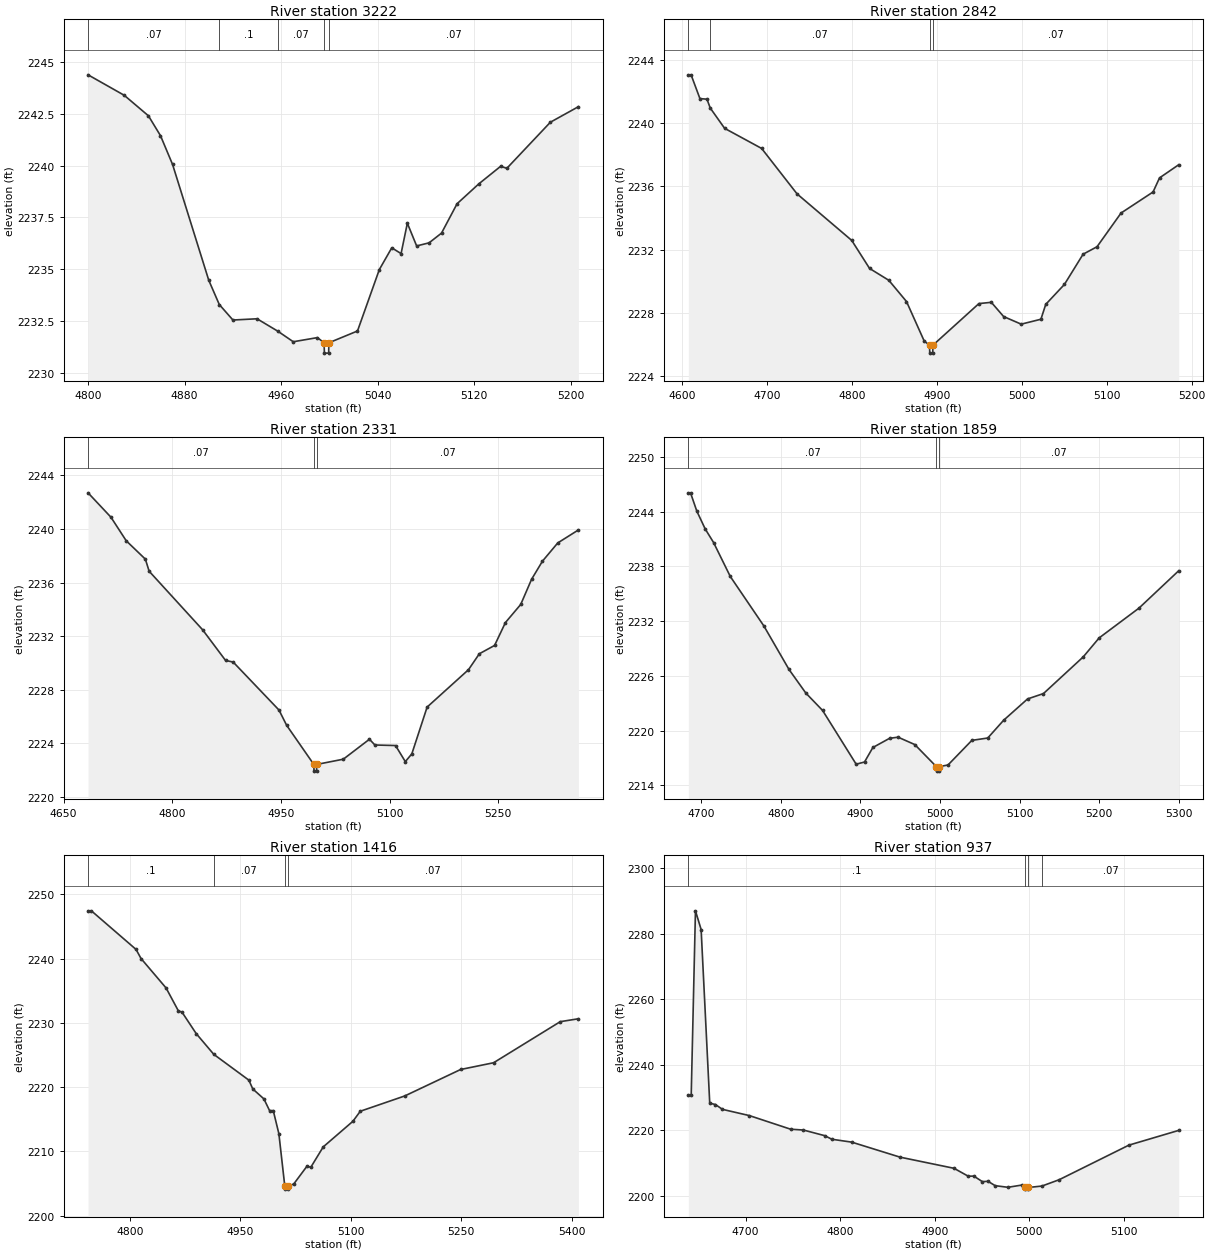
Type RM Length L Ch R = 1,3222,380,380,380
BEGIN DESCRIPTION:
Stream0223 7.0
END DESCRIPTION:
XS GIS Cut Line= 3
      1789175.00     13894825.03      1789175.00     13894625.00
      1789125.00     13894424.99
#Sta/Elev= 30
  4800.0 2244.39  4830.0 2243.40  4850.0 2242.41  4860.0 2241.45  4870.0 2240.06
  4900.0 2234.46  4908.7 2233.29  4920.0 2232.54  4940.0 2232.60  4957.2 2232.00
  4970.0 2231.49  4990.0 2231.69  4995.5 2231.44  4995.8 2230.94  4999.3 2230.94
  4999.5 2231.44  5023.2 2232.01  5041.3 2234.98  5051.6 2236.03  5059.3 2235.75
  5064.5 2237.22  5072.2 2236.12  5082.5 2236.27  5092.8 2236.74  5105.7 2238.16
  5123.7 2239.12  5141.8 2239.97  5146.9 2239.87  5183.0 2242.10  5206.2 2242.85
#Mann=5,-1,0
  4800.0    0.07       0  4908.7     0.1       0  4957.2    0.07       0
  4995.5    0.05       0  4999.5    0.07       0
Bank Sta=4995.5,4999.5
Exp/Cntr=0.3,0.1

Type RM Length L Ch R = 1,2842,511,511,511
BEGIN DESCRIPTION:
Stream0223 6.0
END DESCRIPTION:
XS GIS Cut Line= 3
      1789775.02     13894625.02      1789460.16     13894386.16
      1789375.00     13894224.99
#Sta/Elev= 30
  4607.2 2243.05  4610.4 2243.05  4620.8 2241.55  4629.1 2241.51  4633.0 2240.95
  4649.9 2239.67  4693.5 2238.40  4735.2 2235.53  4799.6 2232.59  4820.6 2230.82
  4843.3 2230.07  4864.1 2228.73  4884.9 2226.24  4891.2 2225.97  4891.5 2225.47
  4895.0 2225.47  4895.2 2225.97  4949.4 2228.60  4964.0 2228.68  4978.5 2227.78
  4999.2 2227.30  5022.4 2227.61  5028.1 2228.55  5050.1 2229.81  5072.1 2231.72
  5088.5 2232.19  5116.8 2234.32  5154.5 2235.65  5162.1 2236.54  5184.7 2237.37
#Mann=4,-1,0
  4607.2     0.1       0  4633.0    0.07       0  4891.2    0.05       0
  4895.2    0.07       0
Bank Sta=4891.2,4895.2
Exp/Cntr=0.3,0.1

Type RM Length L Ch R = 1,2331,472,472,472
BEGIN DESCRIPTION:
Stream0223 5.0
END DESCRIPTION:
XS GIS Cut Line= 3
      1790125.02     13894225.01      1789825.00     13894125.00
      1789525.00     13893925.00
#Sta/Elev= 30
  4683.8 2242.70  4715.4 2240.88  4736.5 2239.12  4762.9 2237.75  4768.1 2236.85
  4841.9 2232.48  4873.6 2230.19  4884.1 2230.07  4947.3 2226.49  4957.9 2225.35
  4995.4 2222.43  4995.7 2221.93  4999.2 2221.93  4999.4 2222.43  5036.1 2222.82
  5072.2 2224.31  5079.7 2223.88  5108.2 2223.84  5121.7 2222.64  5130.7 2223.22
  5151.8 2226.71  5208.9 2229.50  5223.9 2230.69  5244.9 2231.31  5259.9 2233.02
  5281.0 2234.37  5296.0 2236.25  5311.0 2237.60  5332.1 2238.96  5360.6 2239.93
#Mann=3,-1,0
  4683.8    0.07       0  4995.4    0.05       0  4999.4    0.07       0
Bank Sta=4995.4,4999.4
Exp/Cntr=0.3,0.1

Type RM Length L Ch R = 1,1859,443,443,443
BEGIN DESCRIPTION:
Stream0223 4.0
END DESCRIPTION:
XS GIS Cut Line= 3
      1790225.03     13893825.01      1789925.00     13893725.00
      1789624.96     13893725.00
#Sta/Elev= 30
  4683.7 2246.05  4686.4 2246.05  4694.3 2244.05  4704.8 2242.10  4715.4 2240.60
  4736.4 2236.88  4778.6 2231.46  4810.2 2226.69  4831.3 2224.11  4852.4 2222.20
  4894.6 2216.31  4905.1 2216.55  4915.6 2218.14  4936.7 2219.15  4947.3 2219.27
  4968.3 2218.46  4995.3 2216.05  4995.6 2215.55  4999.1 2215.55  4999.3 2216.05
  5010.0 2216.22  5040.0 2218.92  5060.0 2219.18  5080.0 2221.13  5110.0 2223.46
  5130.0 2224.05  5180.0 2228.07  5200.0 2230.15  5250.0 2233.41  5300.0 2237.51
#Mann=3,-1,0
  4683.7    0.07       0  4995.3    0.05       0  4999.3    0.07       0
Bank Sta=4995.3,4999.3
Exp/Cntr=0.3,0.1

Type RM Length L Ch R = 1,1416,479,479,479
BEGIN DESCRIPTION:
Stream0223 3.0
END DESCRIPTION:
XS GIS Cut Line= 3
      1790418.80     13893424.70      1790175.00     13893375.00
      1789760.48     13893334.52
#Sta/Elev= 30
  4743.5 2247.45  4748.0 2247.45  4808.6 2241.44  4815.4 2240.02  4849.4 2235.43
  4865.9 2231.90  4871.1 2231.65  4890.3 2228.32  4914.1 2225.10  4961.7 2221.08
  4967.0 2219.71  4982.1 2218.16  4989.8 2216.33  4994.8 2216.33  5002.4 2212.74
  5010.4 2204.61  5010.7 2204.11  5014.2 2204.11  5014.4 2204.61  5022.5 2204.90
  5040.6 2207.69  5045.7 2207.51  5062.6 2210.69  5102.8 2214.67  5112.9 2216.24
  5173.2 2218.62  5249.0 2222.74  5293.7 2223.79  5384.2 2230.19  5408.8 2230.64
#Mann=4,-1,0
  4743.5     0.1       0  4914.1    0.07       0  5010.4    0.05       0
  5014.4    0.07       0
Bank Sta=5010.4,5014.4
Exp/Cntr=0.3,0.1

Type RM Length L Ch R = 1,937,469,469,469
BEGIN DESCRIPTION:
Stream0223 2.0
END DESCRIPTION:
XS GIS Cut Line= 3
      1790375.02     13893125.01      1790075.00     13892925.00
      1789924.99     13892975.00
#Sta/Elev= 30
  4639.4 2230.60  4642.4 2230.60  4646.9 2287.05  4652.9 2281.34  4662.0 2228.23
  4668.0 2227.82  4675.5 2226.34  4704.0 2224.43  4747.6 2220.27  4761.1 2220.02
  4783.6 2218.30  4791.2 2217.20  4812.2 2216.32  4863.3 2211.73  4920.4 2208.32
  4935.4 2205.91  4941.4 2205.93  4950.4 2204.24  4956.4 2204.34  4963.9 2203.01
  4977.4 2202.51  4992.5 2203.21  4995.0 2202.45  4995.2 2201.95  4998.7 2201.95
  4999.0 2202.45  5013.4 2202.89  5031.6 2204.82  5105.4 2215.40  5158.1 2219.91
#Mann=4,-1,0
  4639.4     0.1       0  4995.0    0.05       0  4999.0     0.1       0
  5013.4    0.07       0
Bank Sta=4995,4999
Exp/Cntr=0.3,0.1

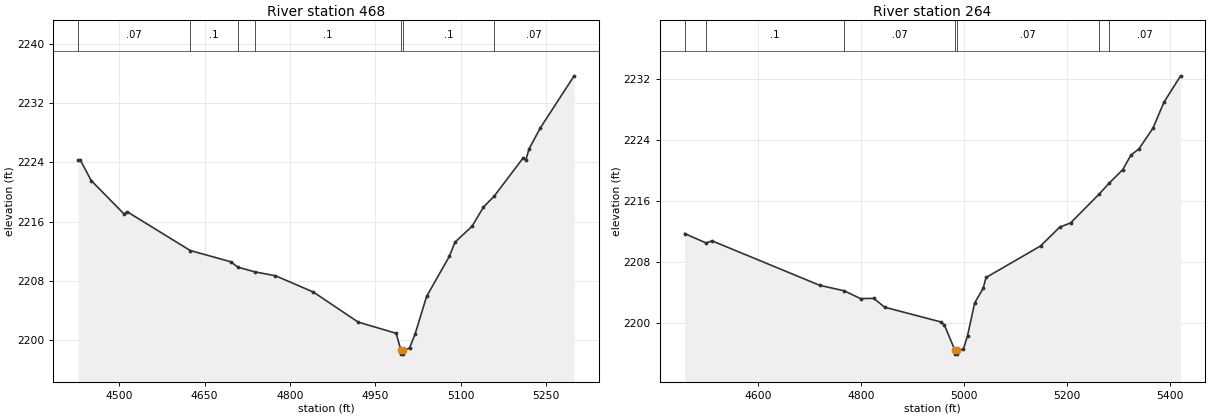
Type RM Length L Ch R = 1,468,204,204,204
BEGIN DESCRIPTION:
Stream0223 1.0
END DESCRIPTION:
XS GIS Cut Line= 3
      1790434.28     13892956.66      1790125.00     13892475.00
      1789825.79     13892468.01
#Sta/Elev= 30
  4427.6 2224.32  4431.5 2224.32  4450.7 2221.55  4508.2 2217.06  4514.1 2217.34
  4624.7 2212.12  4695.8 2210.61  4708.6 2209.87  4738.4 2209.24  4774.4 2208.72
  4841.1 2206.52  4919.7 2202.47  4986.5 2200.96  4995.0 2198.65  4995.3 2198.15
  4998.8 2198.15  4999.0 2198.65  5010.0 2198.97  5020.0 2200.90  5040.0 2205.93
  5080.0 2211.34  5090.0 2213.25  5120.0 2215.40  5140.0 2217.99  5158.7 2219.44
  5209.6 2224.60  5214.6 2224.38  5220.1 2225.83  5240.1 2228.68  5299.3 2235.68
#Mann=7,-1,0
  4427.6    0.07       0  4624.7     0.1       0  4708.6    0.07       0
  4738.4     0.1       0  4995.0    0.05       0  4999.0     0.1       0
  5158.7    0.07       0
Bank Sta=4995,4999
Exp/Cntr=0.3,0.1

Type RM Length L Ch R = 1,264,0,0,0
BEGIN DESCRIPTION:
Stream0223 0.0
END DESCRIPTION:
XS GIS Cut Line= 4
      1790415.05     13892775.06      1790273.48     13892335.65
      1790124.79     13892258.58      1789836.10     13892428.68
#Sta/Elev= 30
  4456.9 2211.76  4498.6 2210.53  4510.4 2210.80  4719.6 2204.99  4767.6 2204.26
  4798.9 2203.25  4824.7 2203.28  4845.7 2202.13  4954.4 2200.21  4961.9 2199.81
  4982.4 2196.49  4982.7 2195.99  4986.2 2195.99  4986.4 2196.49  4998.7 2196.61
  5006.9 2198.39  5020.8 2202.68  5037.3 2204.60  5042.9 2206.01  5148.8 2210.13
  5185.9 2212.58  5207.3 2213.15  5263.1 2216.94  5281.7 2218.31  5308.8 2220.13
  5324.5 2222.01  5340.1 2222.83  5367.4 2225.54  5388.8 2228.94  5421.1 2232.38
#Mann=7,-1,0
  4456.9    0.07       0  4498.6     0.1       0  4767.6    0.07       0
  4982.4    0.05       0  4986.4    0.07       0  5263.1     0.1       0
  5281.7    0.07       0
Bank Sta=4982.4,4986.4
Exp/Cntr=0.3,0.1

Chan Stop Cuts=-1