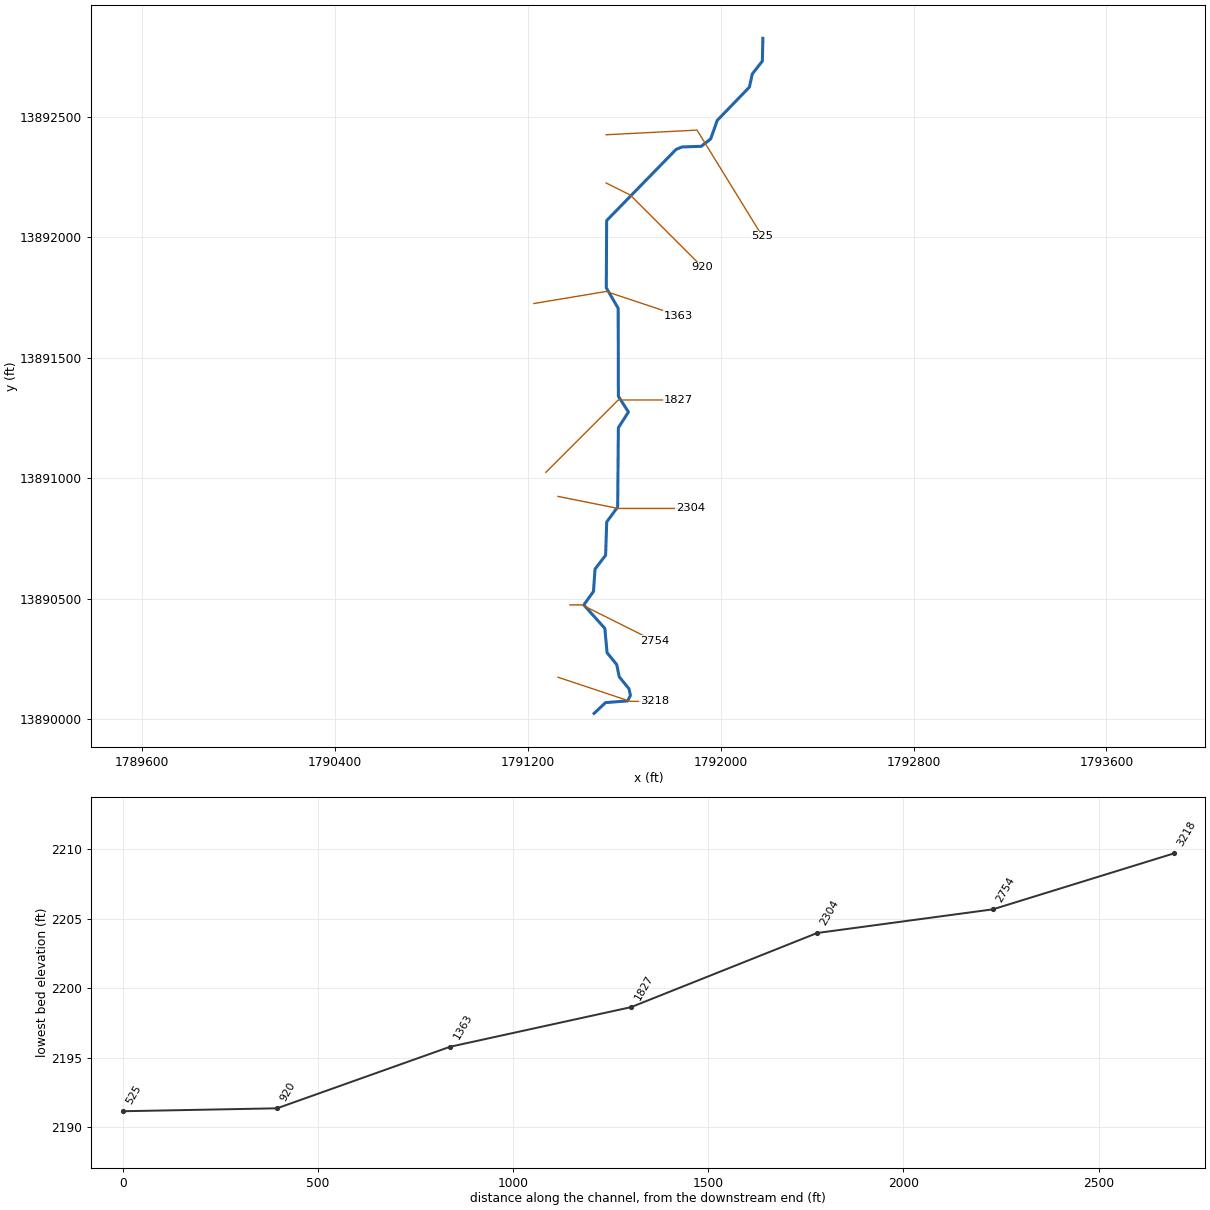
--- Stream0224.prj (project) ---

Proj Title=Stream0224 Base Level Engineering
Current Plan=p01
Default Exp/Contr=0.3,0.1
English Units
Geom File=g01
Flow File=f01
Plan File=p01
BEGIN DESCRIPTION:
Stream0224
END DESCRIPTION:

--- Stream0224.p01 (plan) ---

Plan Title=Multiple Run
Short Identifier=Multiple
Geom File=g01
Flow File=f01
Subcritical Flow
K Sum by GR= 0
Std Step Tol= 0.01
Critical Tol= 0.01
Num of Std Step Trials= 20
Max Error Tol= 0.3
Flow Tol Ratio= 0.001
Split Flow NTrial= 30
Split Flow Tol= 0.02
Split Flow Ratio= 0.02
Log Output Level= 0
Friction Slope Method= 1
Unsteady Friction Slope Method= 2
Unsteady Bridges Friction Slope Method= 1
Parabolic Critical Depth
Global Vel Dist=  1 , 1 , 1
Global Log Level= 0
CheckData=True
Encroach Param= -1, 0, 0, 0
BEGIN DESCRIPTION:
Multiple Run
END DESCRIPTION:

--- Stream0224.f01 (steady flow) ---

Flow Title=Multiple
Number of Profiles=7
Profile Names=10-year,25-year,50-year,1pct_min,100-year,1pct_plu,500-year
River Rch & RM= Stream0224,Reach-1,3218
     787    1307    1789    1183    2361    4711    4065
Boundary for River Rch & Prof#=Stream0224,Reach-1,1
Up Type=0
Dn Type=3
Dn Slope=0.005
Boundary for River Rch & Prof#=Stream0224,Reach-1,2
Up Type=0
Dn Type=3
Dn Slope=0.005
Boundary for River Rch & Prof#=Stream0224,Reach-1,3
Up Type=0
Dn Type=3
Dn Slope=0.005
Boundary for River Rch & Prof#=Stream0224,Reach-1,4
Up Type=0
Dn Type=3
Dn Slope=0.005
Boundary for River Rch & Prof#=Stream0224,Reach-1,5
Up Type=0
Dn Type=3
Dn Slope=0.005
Boundary for River Rch & Prof#=Stream0224,Reach-1,6
Up Type=0
Dn Type=3
Dn Slope=0.005
Boundary for River Rch & Prof#=Stream0224,Reach-1,7
Up Type=0
Dn Type=3
Dn Slope=0.005

--- Stream0224.g01 (geometry) ---

Geom Title=Existing Conditions

River Reach=Stream0224,Reach-1
Reach XY= 30
      1791475.00     13890025.00      1791522.55     13890069.74
      1791613.85     13890076.68      1791625.63     13890099.69
      1791619.85     13890126.80      1791579.23     13890176.69
      1791568.89     13890227.18      1791528.83     13890276.59
      1791519.45     13890377.43      1791432.33     13890474.90
      1791472.44     13890530.89      1791478.85     13890623.40
      1791522.73     13890680.94      1791527.27     13890819.06
      1791572.74     13890880.94      1791575.66     13891209.84
      1791617.44     13891275.00      1791575.66     13891340.16
      1791574.93     13891704.97      1791525.52     13891790.22
      1791527.06     13892069.15      1791815.22     13892364.48
      1791840.22     13892374.47      1791919.29     13892377.08
      1791958.54     13892407.87      1791985.79     13892484.66
      1792119.17     13892622.70      1792131.11     13892677.18
      1792172.93     13892730.86      1792175.00     13892825.00

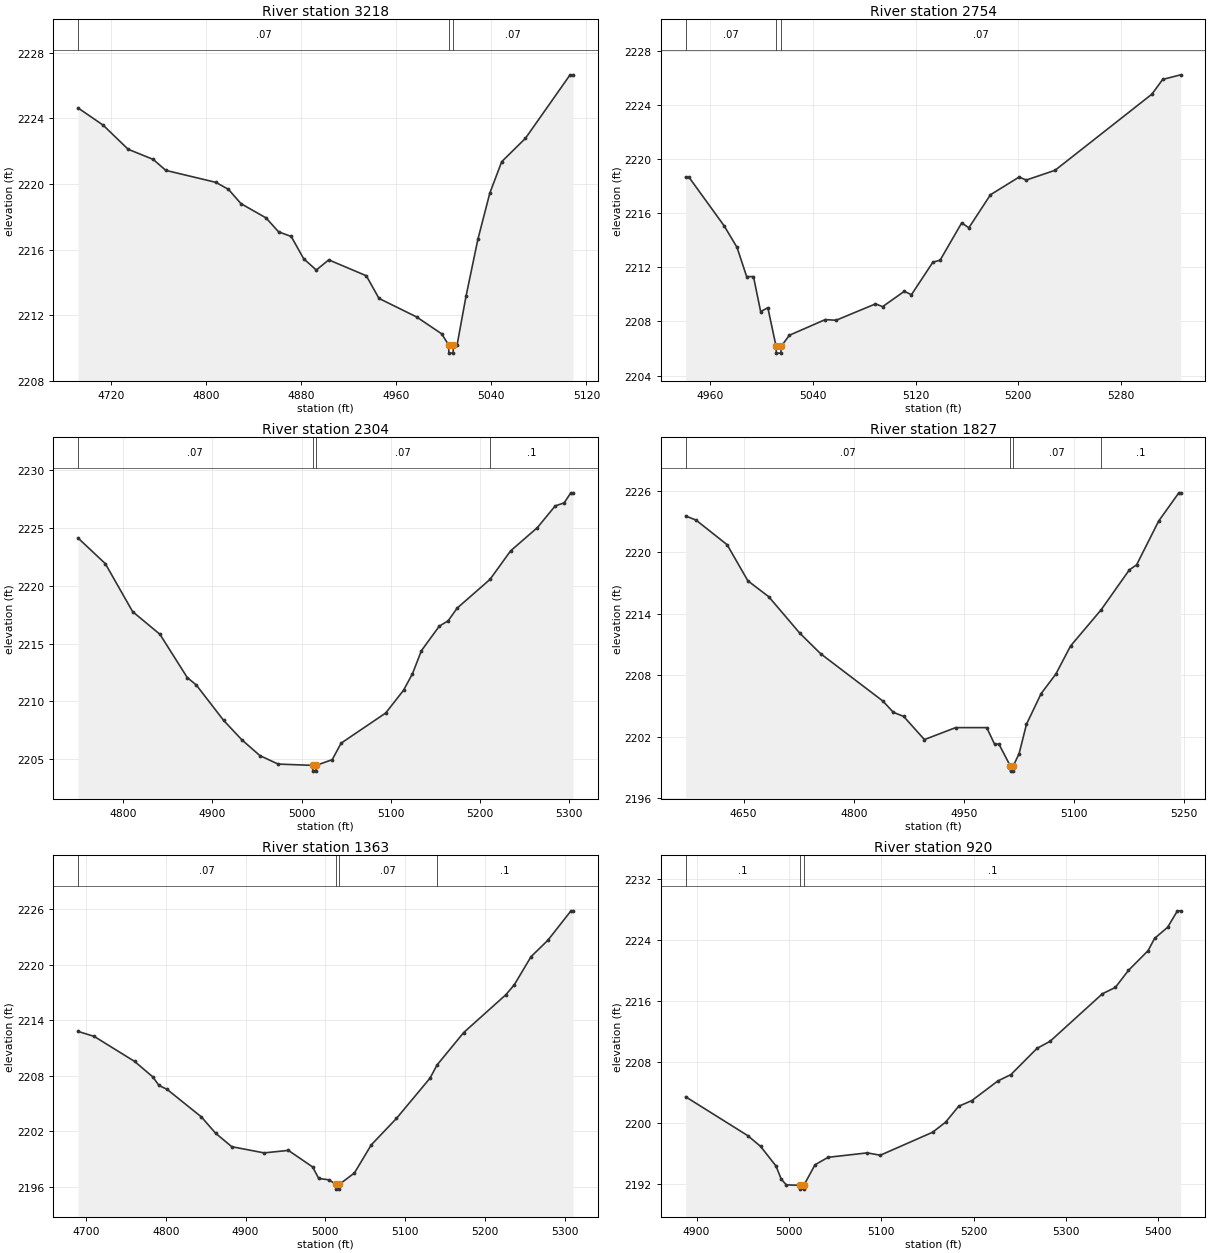
Type RM Length L Ch R = 1,3218,464,464,464
BEGIN DESCRIPTION:
Stream0224 7.0
END DESCRIPTION:
XS GIS Cut Line= 3
      1791325.02     13890174.99      1791625.00     13890075.00
      1791724.99     13890075.00
#Sta/Elev= 30
  4692.6 2224.64  4713.7 2223.59  4734.7 2222.12  4755.8 2221.50  4766.4 2220.83
  4808.5 2220.10  4819.1 2219.67  4829.6 2218.80  4850.7 2217.93  4861.2 2217.08
  4871.8 2216.80  4882.3 2215.44  4892.9 2214.75  4903.4 2215.37  4935.0 2214.40
  4945.6 2213.02  4977.2 2211.89  4998.3 2210.86  5004.2 2210.18  5004.4 2209.68
  5007.9 2209.68  5008.2 2210.18  5011.3 2210.18  5018.8 2213.15  5028.8 2216.63
  5038.8 2219.44  5048.8 2221.36  5068.8 2222.79  5106.3 2226.66  5108.8 2226.66
#Mann=3,-1,0
  4692.6    0.07       0  5004.2    0.05       0  5008.2    0.07       0
Bank Sta=5004.2,5008.2
Exp/Cntr=0.3,0.1

Type RM Length L Ch R = 1,2754,450,450,450
BEGIN DESCRIPTION:
Stream0224 6.0
END DESCRIPTION:
XS GIS Cut Line= 3
      1791375.01     13890475.00      1791425.00     13890475.00
      1791725.00     13890325.00
#Sta/Elev= 30
  4941.0 2218.68  4943.5 2218.68  4971.0 2215.07  4981.0 2213.48  4988.5 2211.32
  4993.8 2211.32  4999.4 2208.73  5005.0 2209.02  5011.4 2206.16  5011.6 2205.66
  5015.1 2205.66  5015.4 2206.16  5021.7 2206.98  5049.7 2208.14  5058.1 2208.09
  5088.8 2209.30  5094.4 2209.10  5111.2 2210.23  5116.8 2209.98  5133.5 2212.39
  5139.1 2212.53  5155.9 2215.29  5161.5 2214.93  5178.3 2217.37  5200.6 2218.68
  5206.2 2218.46  5228.6 2219.18  5304.0 2224.81  5312.4 2225.90  5326.4 2226.24
#Mann=3,-1,0
  4941.0    0.07       0  5011.4    0.05       0  5015.4    0.07       0
Bank Sta=5011.4,5015.4
Exp/Cntr=0.3,0.1

Type RM Length L Ch R = 1,2304,477,477,477
BEGIN DESCRIPTION:
Stream0224 5.0
END DESCRIPTION:
XS GIS Cut Line= 3
      1791325.02     13890925.00      1791575.00     13890875.00
      1791874.97     13890875.00
#Sta/Elev= 30
  4749.3 2224.13  4779.9 2221.91  4810.5 2217.76  4841.1 2215.80  4871.7 2212.06
  4881.9 2211.41  4912.5 2208.35  4932.8 2206.68  4953.2 2205.30  4973.6 2204.57
  5012.2 2204.46  5012.5 2203.96  5016.0 2203.96  5016.2 2204.46  5034.2 2204.95
  5044.2 2206.38  5094.2 2208.99  5114.2 2210.96  5124.2 2212.39  5134.2 2214.38
  5154.2 2216.50  5164.2 2216.97  5174.2 2218.06  5211.1 2220.55  5234.2 2223.02
  5264.2 2225.03  5284.2 2226.91  5294.2 2227.17  5301.7 2228.04  5304.2 2228.04
#Mann=4,-1,0
  4749.3    0.07       0  5012.2    0.05       0  5016.2    0.07       0
  5211.1     0.1       0
Bank Sta=5012.2,5016.2
Exp/Cntr=0.3,0.1

Type RM Length L Ch R = 1,1827,464,464,464
BEGIN DESCRIPTION:
Stream0224 4.0
END DESCRIPTION:
XS GIS Cut Line= 3
      1791275.02     13891025.02      1791575.00     13891325.00
      1791824.97     13891325.00
#Sta/Elev= 30
  4571.0 2223.55  4585.1 2223.15  4627.5 2220.74  4655.8 2217.21  4684.1 2215.67
  4726.5 2212.10  4754.8 2210.10  4839.7 2205.47  4853.8 2204.38  4868.0 2203.97
  4896.2 2201.71  4938.7 2202.88  4981.1 2202.88  4991.7 2201.27  4997.7 2201.27
  5013.2 2199.13  5013.5 2198.63  5017.0 2198.63  5017.2 2199.13  5025.2 2200.35
  5035.2 2203.21  5055.2 2206.21  5075.2 2208.11  5095.2 2210.85  5136.9 2214.39
  5175.2 2218.28  5185.2 2218.78  5215.2 2223.05  5242.7 2225.81  5245.2 2225.81
#Mann=4,-1,0
  4571.0    0.07       0  5013.2    0.05       0  5017.2    0.07       0
  5136.9     0.1       0
Bank Sta=5013.2,5017.2
Exp/Cntr=0.3,0.1

Type RM Length L Ch R = 1,1363,443,443,443
BEGIN DESCRIPTION:
Stream0224 3.0
END DESCRIPTION:
XS GIS Cut Line= 3
      1791225.03     13891725.00      1791525.00     13891775.00
      1791824.96     13891675.01
#Sta/Elev= 30
  4690.1 2212.80  4710.3 2212.26  4761.0 2209.56  4783.8 2207.89  4791.5 2206.97
  4801.6 2206.55  4844.7 2203.57  4862.4 2201.82  4882.7 2200.36  4923.2 2199.69
  4953.7 2199.96  4984.1 2198.17  4991.7 2196.93  5004.8 2196.78  5013.3 2196.28
  5013.5 2195.78  5017.0 2195.78  5017.3 2196.28  5036.4 2197.52  5057.5 2200.55
  5089.1 2203.41  5131.2 2207.76  5140.0 2209.18  5173.4 2212.68  5226.1 2216.75
  5236.7 2217.82  5257.7 2220.86  5278.8 2222.63  5307.8 2225.81  5310.4 2225.81
#Mann=4,-1,0
  4690.1    0.07       0  5013.3    0.05       0  5017.3    0.07       0
  5140.0     0.1       0
Bank Sta=5013.3,5017.3
Exp/Cntr=0.3,0.1

Type RM Length L Ch R = 1,920,395,395,395
BEGIN DESCRIPTION:
Stream0224 2.0
END DESCRIPTION:
XS GIS Cut Line= 3
      1791524.97     13892225.02      1791625.00     13892175.00
      1791925.00     13891875.00
#Sta/Elev= 30
  4888.2 2203.46  4955.3 2198.38  4969.3 2196.97  4986.1 2194.38  4991.7 2192.67
  4997.2 2191.92  5012.2 2191.86  5012.4 2191.36  5015.9 2191.36  5016.2 2191.86
  5028.3 2194.55  5042.5 2195.53  5084.9 2196.11  5099.0 2195.80  5155.6 2198.81
  5169.7 2200.13  5183.9 2202.22  5198.0 2202.95  5226.3 2205.53  5240.5 2206.37
  5268.7 2209.80  5282.9 2210.73  5339.5 2216.95  5353.6 2217.79  5367.7 2220.01
  5389.0 2222.60  5396.0 2224.20  5410.2 2225.67  5420.8 2227.82  5424.3 2227.82
#Mann=3,-1,0
  4888.2     0.1       0  5012.2    0.05       0  5016.2     0.1       0
Bank Sta=5012.2,5016.2
Exp/Cntr=0.3,0.1

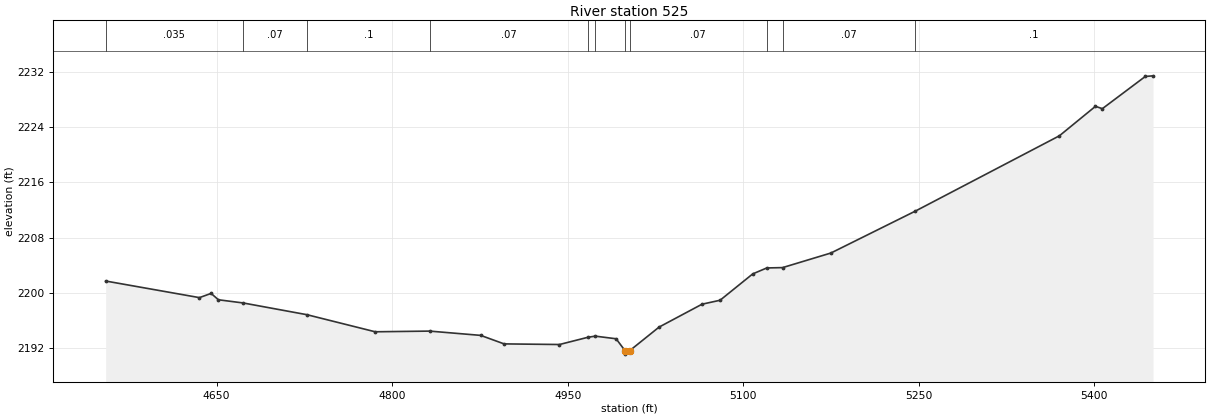
Type RM Length L Ch R = 1,525,0,0,0
BEGIN DESCRIPTION:
Stream0224 1.0
END DESCRIPTION:
XS GIS Cut Line= 3
      1791525.01     13892425.00      1791901.99     13892444.35
      1792173.04     13892003.72
#Sta/Elev= 30
  4555.3 2201.72  4635.4 2199.32  4645.4 2199.93  4651.6 2199.01  4672.7 2198.55
  4727.3 2196.85  4785.6 2194.38  4832.1 2194.48  4875.7 2193.86  4895.7 2192.63
  4943.0 2192.54  4967.4 2193.59  4973.6 2193.75  4991.4 2193.37  4999.0 2191.65
  4999.2 2191.15  5003.0 2191.65  5028.1 2195.06  5064.8 2198.37  5080.2 2198.94
  5108.1 2202.75  5120.1 2203.61  5133.6 2203.66  5174.9 2205.77  5246.8 2211.81
  5370.1 2222.72  5400.9 2226.98  5406.8 2226.64  5443.5 2231.30  5450.1 2231.39
#Mann=11,-1,0
  4555.3   0.035       0  4672.7    0.07       0  4727.3     0.1       0
  4832.1    0.07       0  4967.4     0.1       0  4973.6    0.07       0
  4999.0    0.05       0  5003.0    0.07       0  5120.1     0.1       0
  5133.6    0.07       0  5246.8     0.1       0
Bank Sta=4999,5003
Exp/Cntr=0.3,0.1

Chan Stop Cuts=-1