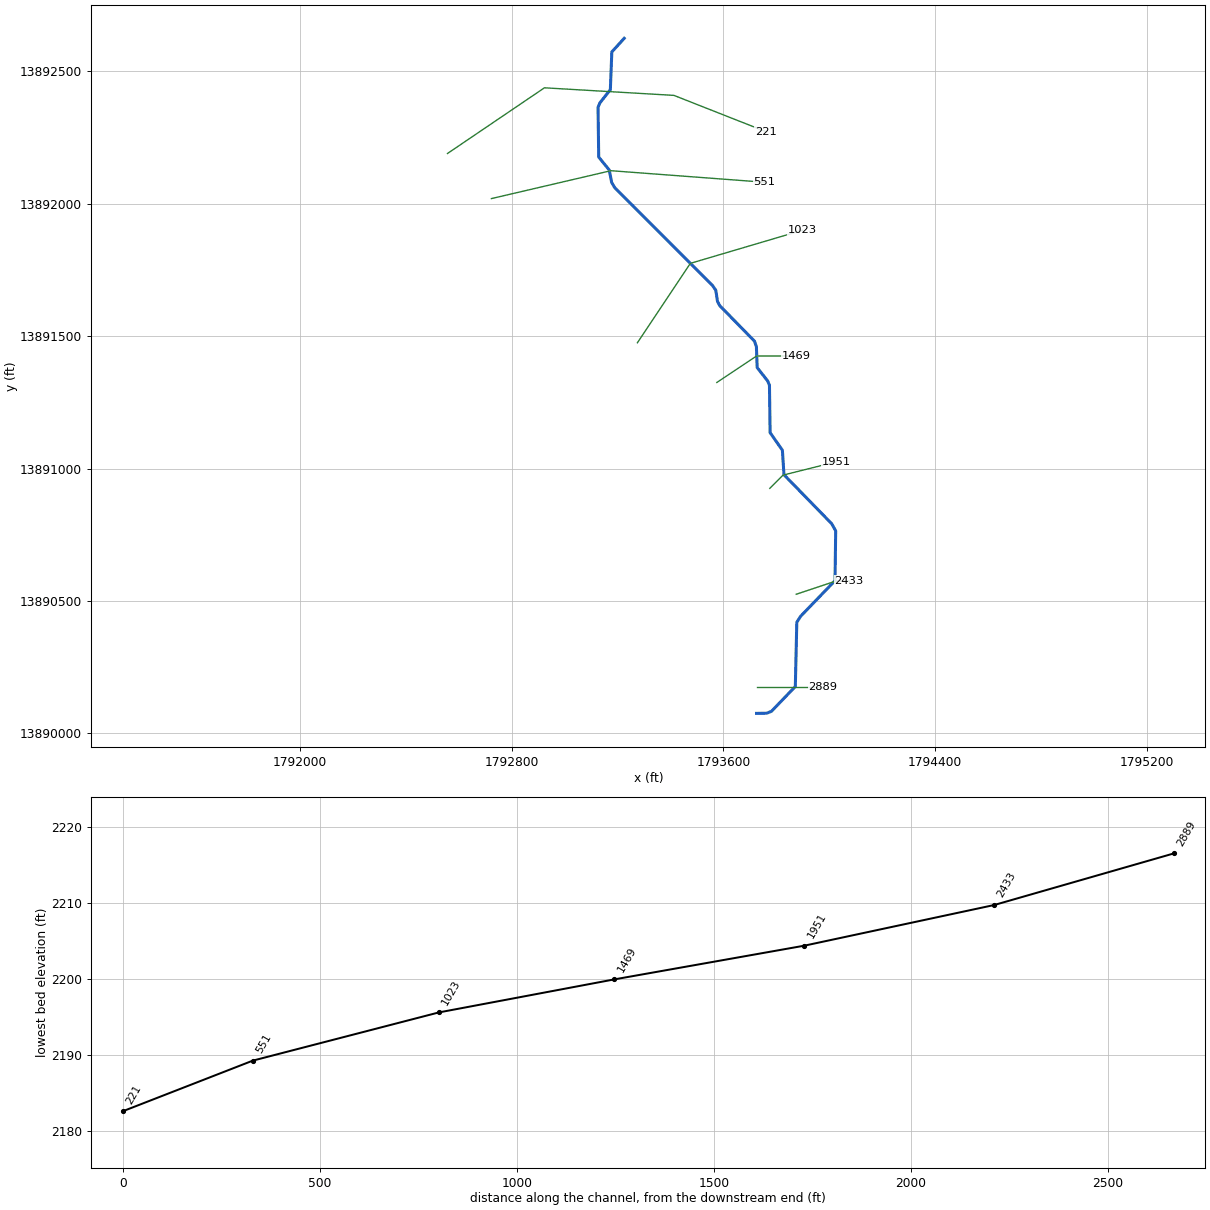
--- Stream0225.prj (project) ---

Proj Title=Stream0225 Base Level Engineering
Current Plan=p01
Default Exp/Contr=0.3,0.1
English Units
Geom File=g01
Flow File=f01
Plan File=p01
BEGIN DESCRIPTION:
Stream0225
END DESCRIPTION:

--- Stream0225.p01 (plan) ---

Plan Title=Multiple Run
Short Identifier=Multiple
Geom File=g01
Flow File=f01
Subcritical Flow
K Sum by GR= 0
Std Step Tol= 0.01
Critical Tol= 0.01
Num of Std Step Trials= 20
Max Error Tol= 0.3
Flow Tol Ratio= 0.001
Split Flow NTrial= 30
Split Flow Tol= 0.02
Split Flow Ratio= 0.02
Log Output Level= 0
Friction Slope Method= 1
Unsteady Friction Slope Method= 2
Unsteady Bridges Friction Slope Method= 1
Parabolic Critical Depth
Global Vel Dist=  1 , 1 , 1
Global Log Level= 0
CheckData=True
Encroach Param= -1, 0, 0, 0
BEGIN DESCRIPTION:
Multiple Run
END DESCRIPTION:

--- Stream0225.f01 (steady flow) ---

Flow Title=Multiple
Number of Profiles=7
Profile Names=10-year,25-year,50-year,1pct_min,100-year,1pct_plu,500-year
River Rch & RM= Stream0225,Reach-1,2889
     605     993    1348     886    1768    3528    3004
Boundary for River Rch & Prof#=Stream0225,Reach-1,1
Up Type=0
Dn Type=3
Dn Slope=0.005
Boundary for River Rch & Prof#=Stream0225,Reach-1,2
Up Type=0
Dn Type=3
Dn Slope=0.005
Boundary for River Rch & Prof#=Stream0225,Reach-1,3
Up Type=0
Dn Type=3
Dn Slope=0.005
Boundary for River Rch & Prof#=Stream0225,Reach-1,4
Up Type=0
Dn Type=3
Dn Slope=0.005
Boundary for River Rch & Prof#=Stream0225,Reach-1,5
Up Type=0
Dn Type=3
Dn Slope=0.005
Boundary for River Rch & Prof#=Stream0225,Reach-1,6
Up Type=0
Dn Type=3
Dn Slope=0.005
Boundary for River Rch & Prof#=Stream0225,Reach-1,7
Up Type=0
Dn Type=3
Dn Slope=0.005

--- Stream0225.g01 (geometry) ---

Geom Title=Existing Conditions

River Reach=Stream0225,Reach-1
Reach XY= 30
      1793725.00     13890075.00      1793763.17     13890075.59
      1793781.24     13890082.75      1793871.48     13890176.45
      1793877.06     13890419.15      1793891.43     13890441.76
      1794021.46     13890576.46      1794023.95     13890764.57
      1794008.57     13890791.76      1793828.61     13890976.50
      1793822.64     13891069.02      1793776.22     13891135.50
      1793773.78     13891314.50      1793766.86     13891331.06
      1793727.36     13891380.98      1793724.48     13891459.78
      1793717.14     13891481.17      1793585.78     13891615.32
      1793577.54     13891631.05      1793571.02     13891673.35
      1793558.35     13891691.67      1793188.62     13892061.78
      1793177.50     13892081.03      1793168.86     13892127.17
      1793128.75     13892176.55      1793126.22     13892364.49
      1793133.14     13892381.06      1793172.73     13892430.94
      1793178.30     13892573.63      1793225.00     13892625.00

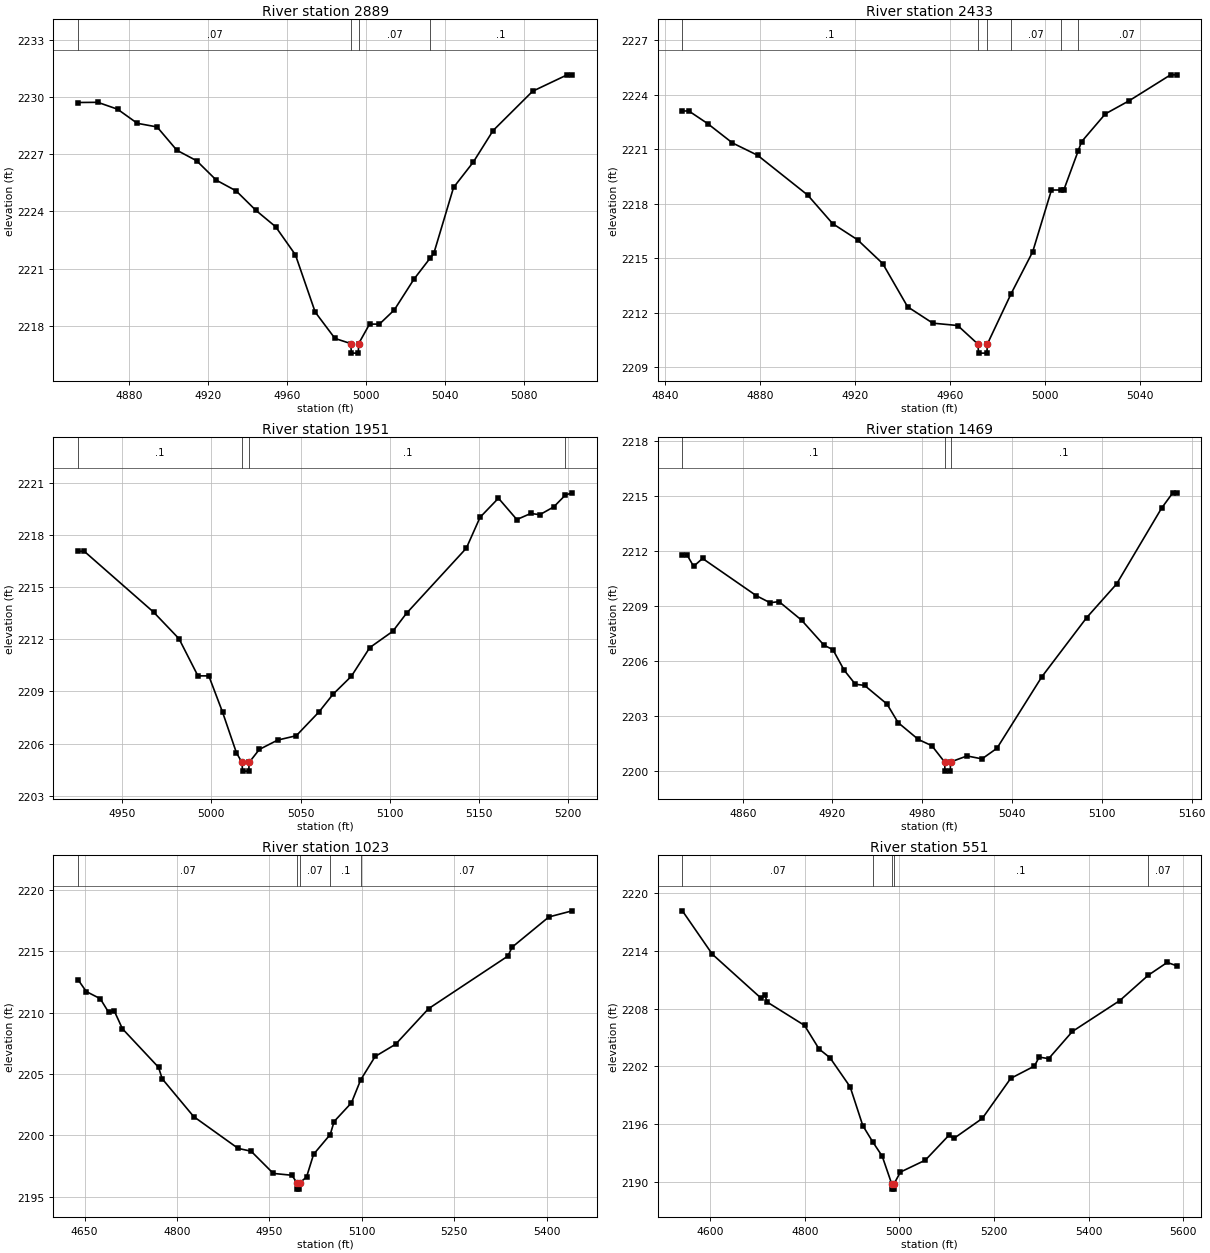
Type RM Length L Ch R = 1,2889,456,456,456
BEGIN DESCRIPTION:
Stream0225 6.0
END DESCRIPTION:
XS GIS Cut Line= 3
      1793724.97     13890175.00      1793875.00     13890175.00
      1793974.97     13890175.00
#Sta/Elev= 30
  4854.2 2229.70  4864.2 2229.71  4874.2 2229.35  4884.2 2228.61  4894.2 2228.42
  4904.2 2227.20  4914.2 2226.65  4924.2 2225.63  4934.2 2225.07  4944.2 2224.05
  4954.2 2223.19  4964.2 2221.72  4974.2 2218.72  4984.2 2217.34  4992.2 2217.07
  4992.5 2216.57  4996.0 2216.57  4996.2 2217.07  5001.7 2218.09  5006.7 2218.09
  5014.2 2218.83  5024.2 2220.45  5032.3 2221.54  5034.2 2221.79  5044.2 2225.25
  5054.2 2226.58  5064.2 2228.23  5084.2 2230.29  5101.7 2231.15  5104.2 2231.15
#Mann=4,-1,0
  4854.2    0.07       0  4992.2    0.05       0  4996.2    0.07       0
  5032.3     0.1       0
Bank Sta=4992.2,4996.2
Exp/Cntr=0.3,0.1

Type RM Length L Ch R = 1,2433,482,482,482
BEGIN DESCRIPTION:
Stream0225 5.0
END DESCRIPTION:
XS GIS Cut Line= 3
      1793874.95     13890524.98      1794025.00     13890575.00
      1794075.04     13890575.00
#Sta/Elev= 27
  4847.2 2223.10  4849.9 2223.10  4857.8 2222.41  4868.3 2221.34  4878.9 2220.66
  4900.0 2218.47  4910.5 2216.90  4921.0 2216.01  4931.6 2214.70  4942.1 2212.32
  4952.7 2211.42  4963.2 2211.29  4971.7 2210.27  4972.0 2209.77  4975.5 2209.77
  4975.7 2210.27  4985.7 2213.04  4994.8 2215.35  5002.7 2218.75  5006.6 2218.75
  5007.9 2218.75  5013.9 2220.88  5015.4 2221.41  5025.4 2222.94  5035.4 2223.66
  5052.9 2225.09  5055.4 2225.09
#Mann=6,-1,0
  4847.2     0.1       0  4971.7    0.05       0  4975.7     0.1       0
  4985.7    0.07       0  5006.6     0.1       0  5013.9    0.07       0
Bank Sta=4971.7,4975.7
Exp/Cntr=0.3,0.1

Type RM Length L Ch R = 1,1951,482,482,482
BEGIN DESCRIPTION:
Stream0225 4.0
END DESCRIPTION:
XS GIS Cut Line= 3
      1793775.00     13890925.00      1793825.00     13890975.00
      1794025.03     13891025.01
#Sta/Elev= 30
  4925.3 2217.08  4928.8 2217.08  4967.7 2213.57  4981.9 2212.04  4992.5 2209.90
  4998.6 2209.90  5006.3 2207.81  5014.1 2205.46  5017.2 2204.91  5017.5 2204.41
  5021.0 2204.41  5021.2 2204.91  5026.9 2205.66  5037.2 2206.20  5047.6 2206.45
  5060.4 2207.83  5068.2 2208.84  5078.5 2209.88  5088.8 2211.53  5101.7 2212.47
  5109.4 2213.51  5142.9 2217.26  5150.6 2219.04  5160.9 2220.14  5171.2 2218.91
  5179.0 2219.26  5184.1 2219.19  5191.9 2219.64  5198.4 2220.32  5202.2 2220.45
#Mann=4,-1,0
  4925.3     0.1       0  5017.2    0.05       0  5021.2     0.1       0
  5198.4    0.07       0
Bank Sta=5017.2,5021.2
Exp/Cntr=0.3,0.1

Type RM Length L Ch R = 1,1469,446,446,446
BEGIN DESCRIPTION:
Stream0225 3.0
END DESCRIPTION:
XS GIS Cut Line= 3
      1793575.02     13891325.02      1793725.00     13891425.00
      1793874.95     13891425.00
#Sta/Elev= 30
  4819.7 2211.81  4822.7 2211.81  4827.2 2211.17  4833.2 2211.60  4869.2 2209.56
  4878.3 2209.18  4884.3 2209.24  4899.3 2208.23  4914.3 2206.86  4920.3 2206.61
  4927.8 2205.49  4935.3 2204.72  4941.4 2204.66  4956.4 2203.64  4963.9 2202.62
  4977.4 2201.70  4986.4 2201.36  4994.9 2200.47  4995.2 2199.97  4998.7 2199.97
  4998.9 2200.47  5009.9 2200.80  5019.9 2200.64  5029.9 2201.22  5059.9 2205.13
  5089.9 2208.37  5109.9 2210.21  5139.9 2214.35  5147.4 2215.19  5149.9 2215.19
#Mann=3,-1,0
  4819.7     0.1       0  4994.9    0.05       0  4998.9     0.1       0
Bank Sta=4994.9,4998.9
Exp/Cntr=0.3,0.1

Type RM Length L Ch R = 1,1023,472,472,472
BEGIN DESCRIPTION:
Stream0225 2.0
END DESCRIPTION:
XS GIS Cut Line= 3
      1793274.99     13891474.98      1793475.00     13891775.00
      1793898.44     13891900.07
#Sta/Elev= 30
  4639.4 2212.68  4652.9 2211.71  4675.5 2211.13  4689.0 2210.03  4698.0 2210.16
  4711.5 2208.68  4770.1 2205.54  4776.1 2204.60  4827.2 2201.52  4899.3 2198.93
  4920.4 2198.70  4956.4 2196.89  4986.5 2196.74  4995.0 2196.11  4995.2 2195.61
  4998.7 2195.61  4999.0 2196.11  5010.4 2196.60  5021.8 2198.45  5048.8 2200.06
  5055.1 2201.12  5083.2 2202.64  5098.3 2204.52  5121.7 2206.42  5155.0 2207.42
  5208.5 2210.32  5337.1 2214.60  5344.1 2215.33  5403.7 2217.79  5441.5 2218.29
#Mann=5,-1,0
  4639.4    0.07       0  4995.0    0.05       0  4999.0    0.07       0
  5048.8     0.1       0  5098.3    0.07       0
Bank Sta=4995,4999
Exp/Cntr=0.3,0.1

Type RM Length L Ch R = 1,551,330,330,330
BEGIN DESCRIPTION:
Stream0225 1.0
END DESCRIPTION:
XS GIS Cut Line= 3
      1792723.46     13892019.61      1793175.00     13892125.00
      1793754.68     13892081.41
#Sta/Elev= 30
  4541.0 2218.16  4604.2 2213.66  4706.9 2209.11  4715.4 2209.40  4720.5 2208.68
  4799.3 2206.26  4830.1 2203.81  4853.2 2202.90  4895.8 2199.88  4922.5 2195.86
  4943.1 2194.20  4963.6 2192.68  4984.0 2189.76  4984.2 2189.26  4987.7 2189.26
  4988.0 2189.76  5002.1 2191.03  5054.8 2192.27  5105.0 2194.87  5115.0 2194.52
  5175.2 2196.60  5235.3 2200.76  5285.5 2202.04  5295.5 2202.97  5315.6 2202.81
  5365.7 2205.63  5466.0 2208.84  5526.4 2211.48  5566.3 2212.80  5586.0 2212.46
#Mann=5,-1,0
  4541.0    0.07       0  4943.1     0.1       0  4984.0    0.05       0
  4988.0     0.1       0  5526.4    0.07       0
Bank Sta=4984,4988
Exp/Cntr=0.3,0.1

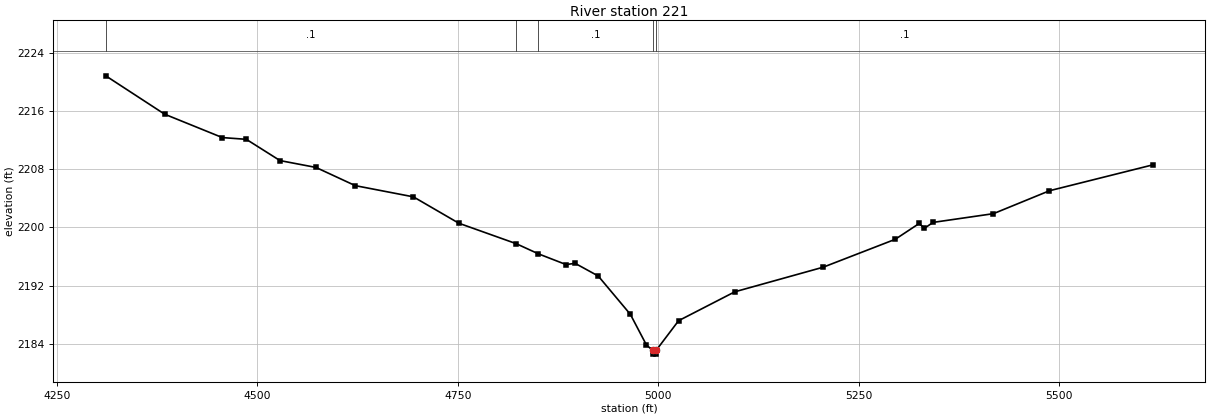
Type RM Length L Ch R = 1,221,0,0,0
BEGIN DESCRIPTION:
Stream0225 0.0
END DESCRIPTION:
XS GIS Cut Line= 4
      1792557.54     13892189.99      1792923.78     13892438.12
      1793412.84     13892409.50      1793760.19     13892272.69
#Sta/Elev= 30
  4311.2 2220.81  4384.6 2215.54  4456.5 2212.33  4486.4 2212.09  4528.4 2209.17
  4573.2 2208.23  4622.2 2205.73  4694.7 2204.19  4751.3 2200.57  4822.6 2197.77
  4850.6 2196.36  4885.0 2194.89  4896.3 2195.06  4925.1 2193.32  4965.2 2188.05
  4985.2 2183.85  4993.2 2183.09  4993.5 2182.59  4997.0 2182.59  4997.2 2183.09
  5025.3 2187.18  5095.4 2191.15  5205.6 2194.53  5295.4 2198.36  5325.2 2200.53
  5331.8 2199.87  5342.5 2200.68  5417.8 2201.88  5487.7 2205.03  5616.8 2208.59
#Mann=5,-1,0
  4311.2     0.1       0  4822.6    0.07       0  4850.6     0.1       0
  4993.2    0.05       0  4997.2     0.1       0
Bank Sta=4993.2,4997.2
Exp/Cntr=0.3,0.1

Chan Stop Cuts=-1