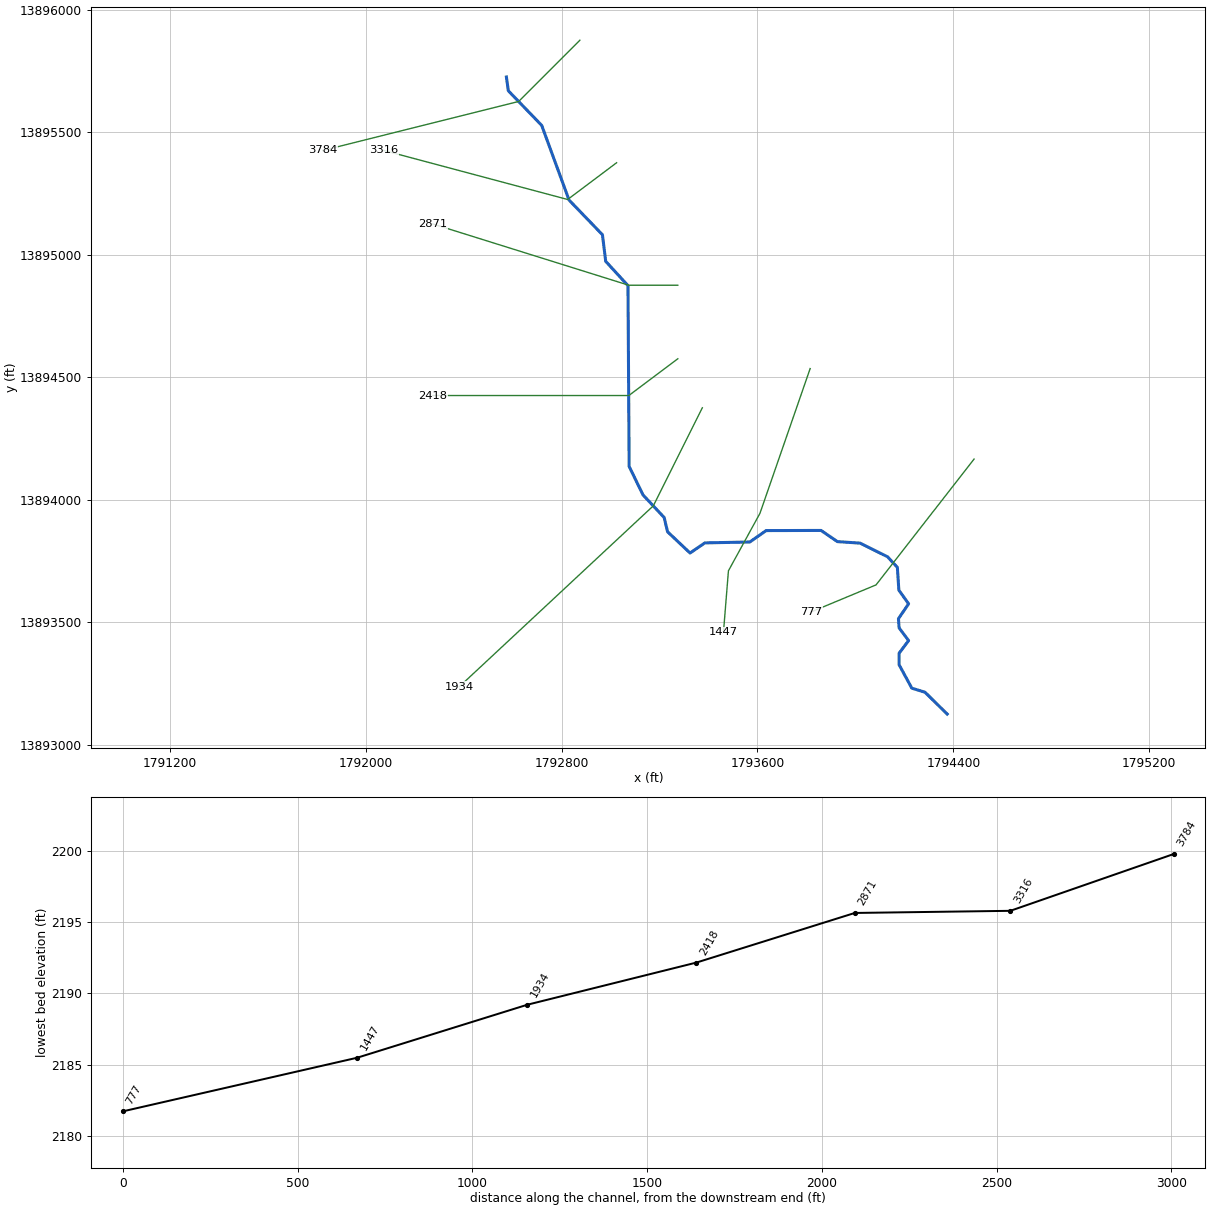
--- Stream0226.prj (project) ---

Proj Title=Stream0226 Base Level Engineering
Current Plan=p01
Default Exp/Contr=0.3,0.1
English Units
Geom File=g01
Flow File=f01
Plan File=p01
BEGIN DESCRIPTION:
Stream0226
END DESCRIPTION:

--- Stream0226.p01 (plan) ---

Plan Title=Multiple Run
Short Identifier=Multiple
Geom File=g01
Flow File=f01
Subcritical Flow
K Sum by GR= 0
Std Step Tol= 0.01
Critical Tol= 0.01
Num of Std Step Trials= 20
Max Error Tol= 0.3
Flow Tol Ratio= 0.001
Split Flow NTrial= 30
Split Flow Tol= 0.02
Split Flow Ratio= 0.02
Log Output Level= 0
Friction Slope Method= 1
Unsteady Friction Slope Method= 2
Unsteady Bridges Friction Slope Method= 1
Parabolic Critical Depth
Global Vel Dist=  1 , 1 , 1
Global Log Level= 0
CheckData=True
Encroach Param= -1, 0, 0, 0
BEGIN DESCRIPTION:
Multiple Run
END DESCRIPTION:

--- Stream0226.f01 (steady flow) ---

Flow Title=Multiple
Number of Profiles=7
Profile Names=10-year,25-year,50-year,1pct_min,100-year,1pct_plu,500-year
River Rch & RM= Stream0226,Reach-1,3784
    1390    2407    3386    2300    4588    9155    8334
Boundary for River Rch & Prof#=Stream0226,Reach-1,1
Up Type=0
Dn Type=3
Dn Slope=0.005
Boundary for River Rch & Prof#=Stream0226,Reach-1,2
Up Type=0
Dn Type=3
Dn Slope=0.005
Boundary for River Rch & Prof#=Stream0226,Reach-1,3
Up Type=0
Dn Type=3
Dn Slope=0.005
Boundary for River Rch & Prof#=Stream0226,Reach-1,4
Up Type=0
Dn Type=3
Dn Slope=0.005
Boundary for River Rch & Prof#=Stream0226,Reach-1,5
Up Type=0
Dn Type=3
Dn Slope=0.005
Boundary for River Rch & Prof#=Stream0226,Reach-1,6
Up Type=0
Dn Type=3
Dn Slope=0.005
Boundary for River Rch & Prof#=Stream0226,Reach-1,7
Up Type=0
Dn Type=3
Dn Slope=0.005

--- Stream0226.g01 (geometry) ---

Geom Title=Existing Conditions

River Reach=Stream0226,Reach-1
Reach XY= 30
      1792575.00     13895725.00      1792582.76     13895668.79
      1792719.17     13895527.30      1792830.83     13895222.70
      1792967.14     13895081.17      1792980.54     13894972.58
      1793071.45     13894873.53      1793076.20     13894135.50
      1793133.16     13894018.95      1793219.13     13893927.28
      1793233.16     13893868.91      1793324.89     13893782.31
      1793385.43     13893823.61      1793569.06     13893827.26
      1793635.50     13893873.78      1793859.78     13893874.48
      1793926.60     13893828.86      1794019.04     13893822.67
      1794131.38     13893767.00      1794171.48     13893723.72
      1794177.56     13893630.90      1794217.41     13893574.99
      1794175.98     13893514.36      1794178.64     13893476.65
      1794217.38     13893425.00      1794178.60     13893373.36
      1794178.36     13893326.71      1794230.58     13893230.60
      1794284.42     13893214.17      1794375.00     13893125.00

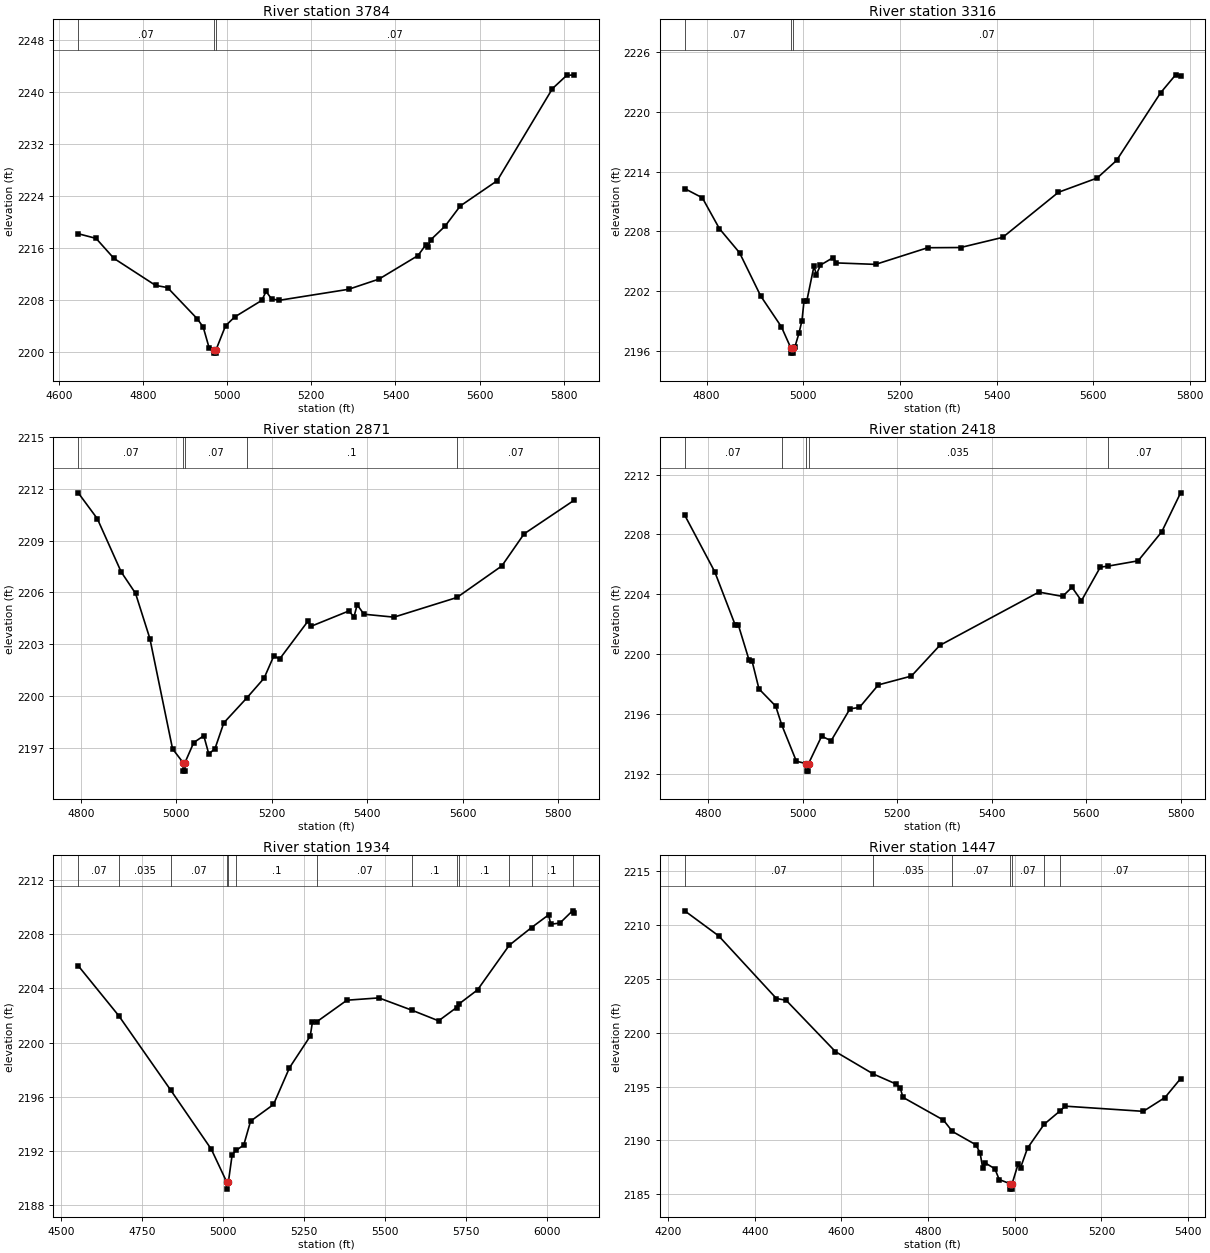
Type RM Length L Ch R = 1,3784,468,468,468
BEGIN DESCRIPTION:
Stream0226 5.0
END DESCRIPTION:
XS GIS Cut Line= 3
      1792874.97     13895874.97      1792625.00     13895625.00
      1791825.04     13895425.01
#Sta/Elev= 30
  4646.3 2218.19  4688.7 2217.47  4731.1 2214.39  4830.1 2210.22  4858.4 2209.89
  4929.1 2205.07  4943.2 2203.80  4957.4 2200.57  4969.5 2200.28  4969.7 2199.78
  4973.3 2199.78  4973.6 2200.28  4996.3 2204.00  5017.9 2205.35  5082.3 2207.91
  5092.6 2209.29  5105.5 2208.15  5123.5 2207.92  5288.4 2209.62  5360.6 2211.19
  5453.4 2214.82  5471.4 2216.42  5476.6 2216.17  5484.3 2217.29  5517.8 2219.36
  5553.9 2222.47  5641.5 2226.36  5772.9 2240.57  5806.4 2242.59  5824.4 2242.69
#Mann=3,-1,0
  4646.3    0.07       0  4969.5    0.05       0  4973.6    0.07       0
Bank Sta=4969.5,4973.6
Exp/Cntr=0.3,0.1

Type RM Length L Ch R = 1,3316,445,445,445
BEGIN DESCRIPTION:
Stream0226 4.0
END DESCRIPTION:
XS GIS Cut Line= 3
      1793024.99     13895375.00      1792825.00     13895225.00
      1792075.00     13895425.00
#Sta/Elev= 30
  4754.5 2212.29  4791.0 2211.37  4826.4 2208.27  4868.0 2205.86  4911.8 2201.52
  4954.5 2198.44  4974.3 2196.29  4974.6 2195.79  4978.2 2195.79  4978.4 2196.29
  4982.6 2196.42  4991.0 2197.79  4997.2 2199.06  5001.4 2201.00  5007.1 2201.00
  5022.0 2204.50  5027.1 2203.67  5035.5 2204.62  5062.1 2205.38  5067.2 2204.84
  5149.4 2204.69  5257.4 2206.36  5325.3 2206.38  5412.6 2207.40  5527.8 2211.92
  5608.0 2213.35  5648.1 2215.11  5739.3 2221.90  5770.4 2223.70  5780.7 2223.57
#Mann=3,-1,0
  4754.5    0.07       0  4974.3    0.05       0  4978.4    0.07       0
Bank Sta=4974.3,4978.4
Exp/Cntr=0.3,0.1

Type RM Length L Ch R = 1,2871,453,453,453
BEGIN DESCRIPTION:
Stream0226 3.0
END DESCRIPTION:
XS GIS Cut Line= 3
      1793275.01     13894875.00      1793075.00     13894875.00
      1792274.97     13895125.01
#Sta/Elev= 30
  4794.7 2211.78  4834.7 2210.28  4884.7 2207.19  4914.7 2205.95  4944.7 2203.33
  4992.2 2196.93  5014.1 2196.14  5014.3 2195.64  5018.0 2195.64  5018.3 2196.14
  5036.6 2197.30  5057.6 2197.69  5068.1 2196.63  5081.1 2196.95  5099.5 2198.44
  5147.8 2199.89  5183.8 2201.03  5204.3 2202.33  5216.3 2202.14  5276.0 2204.35
  5281.3 2204.03  5361.4 2204.93  5371.9 2204.58  5378.7 2205.29  5392.8 2204.74
  5455.7 2204.57  5587.5 2205.71  5681.5 2207.54  5728.1 2209.40  5832.9 2211.35
#Mann=5,-1,0
  4794.7    0.07       0  5014.1    0.05       0  5018.3    0.07       0
  5147.8     0.1       0  5587.5    0.07       0
Bank Sta=5014.1,5018.3
Exp/Cntr=0.3,0.1

Type RM Length L Ch R = 1,2418,484,484,484
BEGIN DESCRIPTION:
Stream0226 2.0
END DESCRIPTION:
XS GIS Cut Line= 3
      1793275.00     13894575.00      1793075.00     13894425.00
      1792275.00     13894425.00
#Sta/Elev= 30
  4750.0 2209.29  4813.5 2205.51  4857.3 2201.91  4863.5 2201.95  4886.5 2199.57
  4892.7 2199.52  4907.3 2197.66  4942.7 2196.51  4955.5 2195.25  4986.5 2192.82
  5007.9 2192.66  5008.2 2192.16  5011.9 2192.16  5012.2 2192.66  5040.0 2194.50
  5060.0 2194.19  5100.0 2196.33  5120.0 2196.42  5160.0 2197.93  5230.0 2198.52
  5290.0 2200.57  5500.0 2204.14  5550.0 2203.85  5570.0 2204.46  5590.0 2203.56
  5630.0 2205.81  5645.2 2205.87  5710.0 2206.23  5760.0 2208.17  5800.0 2210.78
#Mann=5,-1,0
  4750.0    0.07       0  4955.5   0.035       0  5007.9   0.035       0
  5012.2   0.035       0  5645.2    0.07       0
Bank Sta=5007.9,5012.2
Exp/Cntr=0.3,0.1

Type RM Length L Ch R = 1,1934,487,487,487
BEGIN DESCRIPTION:
Stream0226 1.0
END DESCRIPTION:
XS GIS Cut Line= 3
      1793374.99     13894374.99      1793175.00     13893975.00
      1792382.12     13893236.25
#Sta/Elev= 30
  4552.8 2205.67  4677.8 2201.99  4838.3 2196.50  4963.7 2192.14  5011.7 2189.70
  5012.0 2189.20  5016.2 2189.70  5028.1 2191.75  5040.0 2192.05  5063.8 2192.45
  5084.8 2194.21  5155.6 2195.44  5205.0 2198.15  5269.0 2200.48  5275.8 2201.52
  5288.6 2201.53  5382.3 2203.13  5481.0 2203.30  5584.2 2202.38  5665.2 2201.61
  5720.8 2202.59  5729.1 2202.87  5785.4 2203.89  5883.3 2207.18  5952.3 2208.49
  6004.7 2209.42  6011.6 2208.73  6039.9 2208.82  6078.6 2209.72  6083.7 2209.59
#Mann=13,-1,0
  4552.8    0.07       0  4677.8   0.035       0  4838.3    0.07       0
  5011.7    0.05       0  5016.2    0.07       0  5040.0     0.1       0
  5288.6    0.07       0  5584.2     0.1       0  5720.8    0.07       0
  5729.1     0.1       0  5883.3    0.07       0  5952.3     0.1       0
  6078.6    0.07       0
Bank Sta=5011.7,5016.2
Exp/Cntr=0.3,0.1

Type RM Length L Ch R = 1,1447,670,670,670
BEGIN DESCRIPTION:
Stream0226 0.0
END DESCRIPTION:
XS GIS Cut Line= 4
      1793815.36     13894534.96      1793610.43     13893944.39
      1793481.64     13893709.66      1793461.37     13893459.03
#Sta/Elev= 30
  4238.3 2211.31  4316.6 2208.99  4450.0 2203.17  4472.3 2203.01  4586.2 2198.24
  4673.8 2196.16  4725.2 2195.25  4735.8 2194.85  4741.9 2194.00  4835.3 2191.89
  4856.1 2190.83  4910.0 2189.60  4919.8 2188.86  4926.1 2187.41  4931.8 2187.91
  4954.0 2187.37  4964.0 2186.37  4989.2 2185.98  4989.5 2185.48  4993.4 2185.48
  4993.8 2185.98  5007.6 2187.80  5013.3 2187.47  5029.4 2189.29  5067.7 2191.50
  5104.7 2192.75  5116.6 2193.18  5296.4 2192.70  5346.5 2193.98  5382.6 2195.74
#Mann=7,-1,0
  4238.3    0.07       0  4673.8   0.035       0  4856.1    0.07       0
  4989.2    0.05       0  4993.8    0.07       0  5067.7     0.1       0
  5104.7    0.07       0
Bank Sta=4989.2,4993.8
Exp/Cntr=0.3,0.1

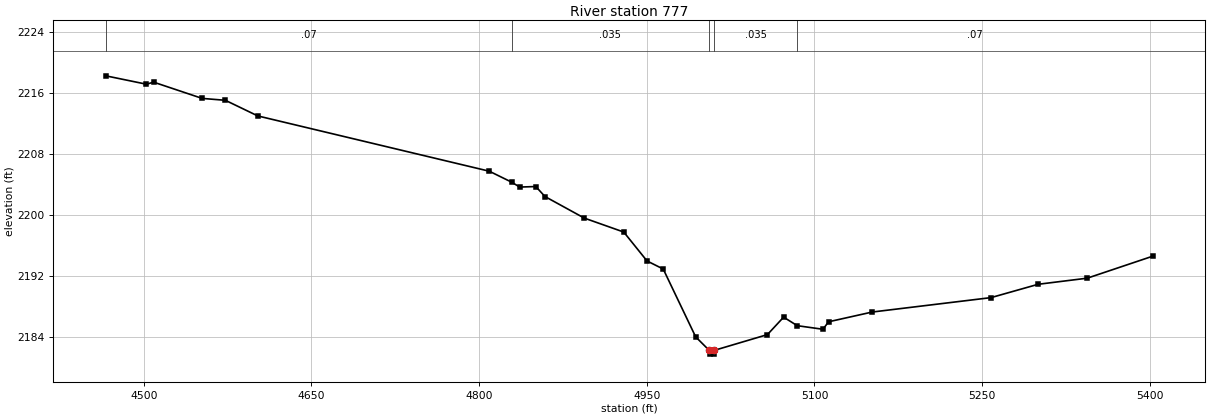
Type RM Length L Ch R = 1,777,0,0,0
BEGIN DESCRIPTION:
Stream0226 0.1
END DESCRIPTION:
XS GIS Cut Line= 3
      1794484.76     13894165.71      1794084.41     13893652.17
      1793820.59     13893542.41
#Sta/Elev= 30
  4466.0 2218.22  4502.4 2217.12  4508.8 2217.39  4552.2 2215.26  4573.0 2215.01
  4602.0 2212.96  4809.1 2205.71  4829.0 2204.28  4836.3 2203.63  4850.7 2203.70
  4858.9 2202.39  4894.1 2199.56  4929.4 2197.73  4950.2 2193.94  4964.7 2192.88
  4993.7 2183.99  5005.8 2182.22  5006.1 2181.72  5010.1 2181.72  5010.5 2182.22
  5057.9 2184.28  5072.4 2186.57  5084.6 2185.45  5107.6 2184.98  5112.6 2185.96
  5151.6 2187.24  5257.9 2189.13  5300.1 2190.88  5344.0 2191.68  5402.9 2194.58
#Mann=5,-1,0
  4466.0    0.07       0  4829.0   0.035       0  5005.8   0.035       0
  5010.5   0.035       0  5084.6    0.07       0
Bank Sta=5005.8,5010.5
Exp/Cntr=0.3,0.1

Chan Stop Cuts=-1