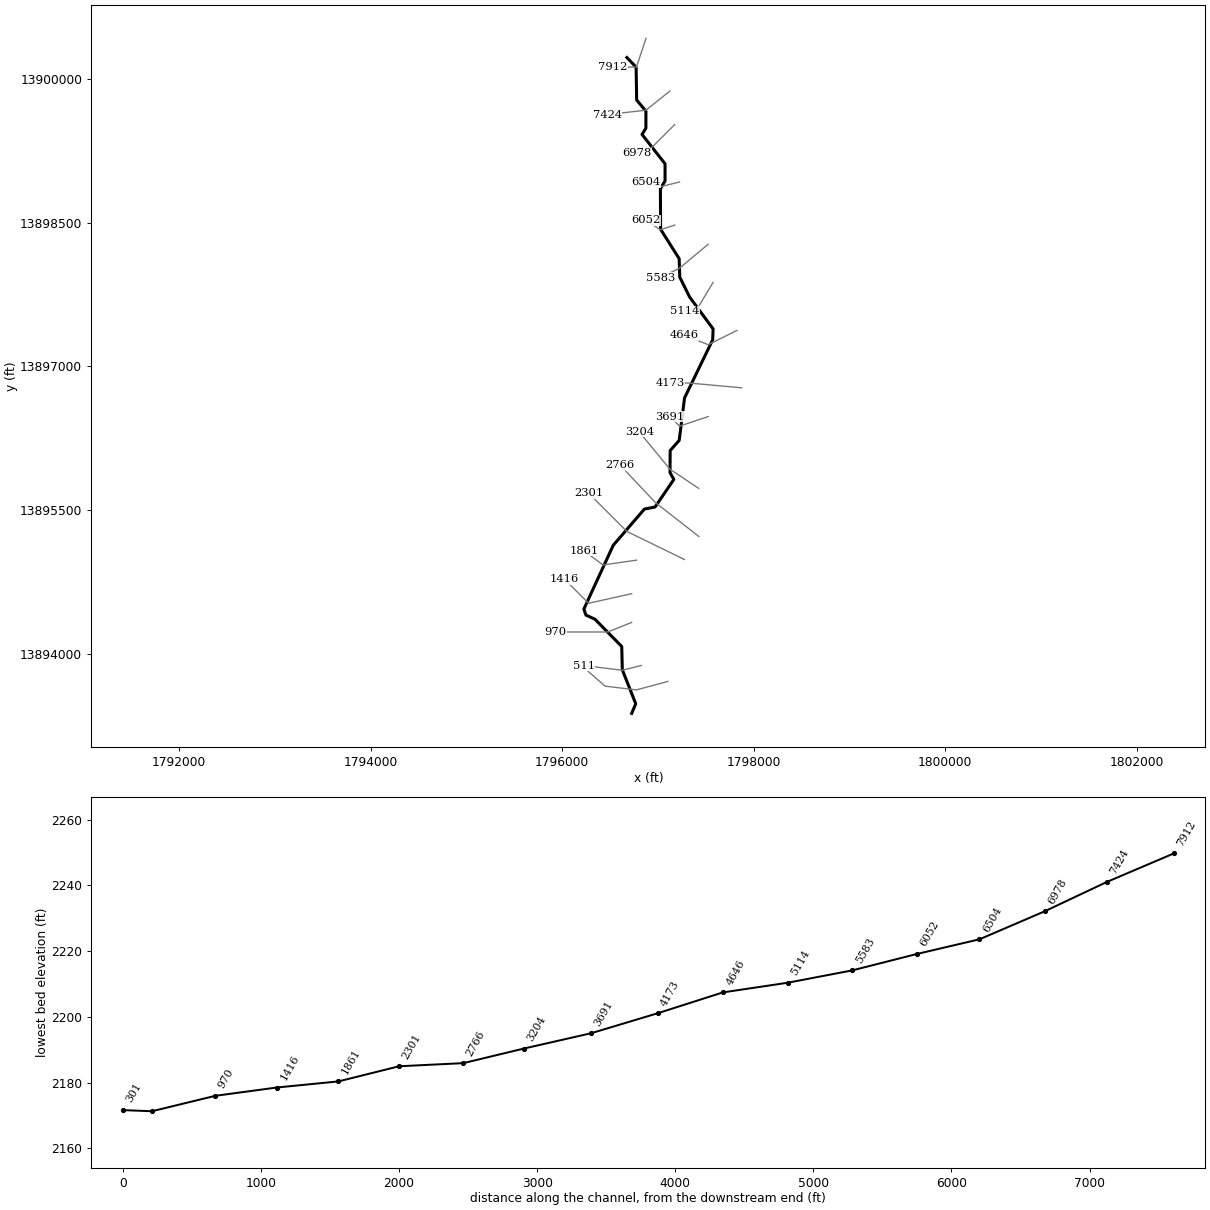
--- Stream0227.prj (project) ---

Proj Title=Stream0227 Base Level Engineering
Current Plan=p01
Default Exp/Contr=0.3,0.1
English Units
Geom File=g01
Flow File=f01
Plan File=p01
BEGIN DESCRIPTION:
Stream0227
END DESCRIPTION:

--- Stream0227.p01 (plan) ---

Plan Title=Multiple Run
Short Identifier=Multiple
Geom File=g01
Flow File=f01
Subcritical Flow
K Sum by GR= 0
Std Step Tol= 0.01
Critical Tol= 0.01
Num of Std Step Trials= 20
Max Error Tol= 0.3
Flow Tol Ratio= 0.001
Split Flow NTrial= 30
Split Flow Tol= 0.02
Split Flow Ratio= 0.02
Log Output Level= 0
Friction Slope Method= 1
Unsteady Friction Slope Method= 2
Unsteady Bridges Friction Slope Method= 1
Parabolic Critical Depth
Global Vel Dist=  1 , 1 , 1
Global Log Level= 0
CheckData=True
Encroach Param= -1, 0, 0, 0
BEGIN DESCRIPTION:
Multiple Run
END DESCRIPTION:

--- Stream0227.f01 (steady flow) ---

Flow Title=Multiple
Number of Profiles=7
Profile Names=10-year,25-year,50-year,1pct_min,100-year,1pct_plu,500-year
River Rch & RM= Stream0227,Reach-1,7912
     563     923    1252     823    1641    3275    2786
River Rch & RM= Stream0227,Reach-1,6052
    1058    1798    2498    1677    3346    6675    5934
River Rch & RM= Stream0227,Reach-1,2301
    1297    2227    3115    2103    4196    8372    7530
Boundary for River Rch & Prof#=Stream0227,Reach-1,1
Up Type=0
Dn Type=3
Dn Slope=0.005
Boundary for River Rch & Prof#=Stream0227,Reach-1,2
Up Type=0
Dn Type=3
Dn Slope=0.005
Boundary for River Rch & Prof#=Stream0227,Reach-1,3
Up Type=0
Dn Type=3
Dn Slope=0.005
Boundary for River Rch & Prof#=Stream0227,Reach-1,4
Up Type=0
Dn Type=3
Dn Slope=0.005
Boundary for River Rch & Prof#=Stream0227,Reach-1,5
Up Type=0
Dn Type=3
Dn Slope=0.005
Boundary for River Rch & Prof#=Stream0227,Reach-1,6
Up Type=0
Dn Type=3
Dn Slope=0.005
Boundary for River Rch & Prof#=Stream0227,Reach-1,7
Up Type=0
Dn Type=3
Dn Slope=0.005

--- Stream0227.g01 (geometry) ---

Geom Title=Existing Conditions

River Reach=Stream0227,Reach-1
Reach XY= 30
      1796675.00     13900225.00      1796771.52     13900123.56
      1796777.07     13899780.86      1796873.95     13899664.56
      1796873.62     13899485.44      1796833.04     13899421.68
      1797073.95     13899114.57      1797073.78     13898935.51
      1797025.07     13898854.97      1797027.24     13898430.93
      1797221.25     13898123.45      1797227.24     13897930.93
      1797330.85     13897722.71      1797575.53     13897390.19
      1797571.26     13897276.56      1797277.26     13896669.06
      1797221.45     13896226.47      1797127.07     13896119.14
      1797125.66     13895890.16      1797165.59     13895818.38
      1796969.52     13895530.26      1796857.90     13895508.69
      1796533.14     13895131.06      1796225.68     13894464.25
      1796247.55     13894401.16      1796341.66     13894358.34
      1796621.46     13894073.54      1796627.26     13893830.94
      1796767.72     13893474.97      1796725.00     13893375.00

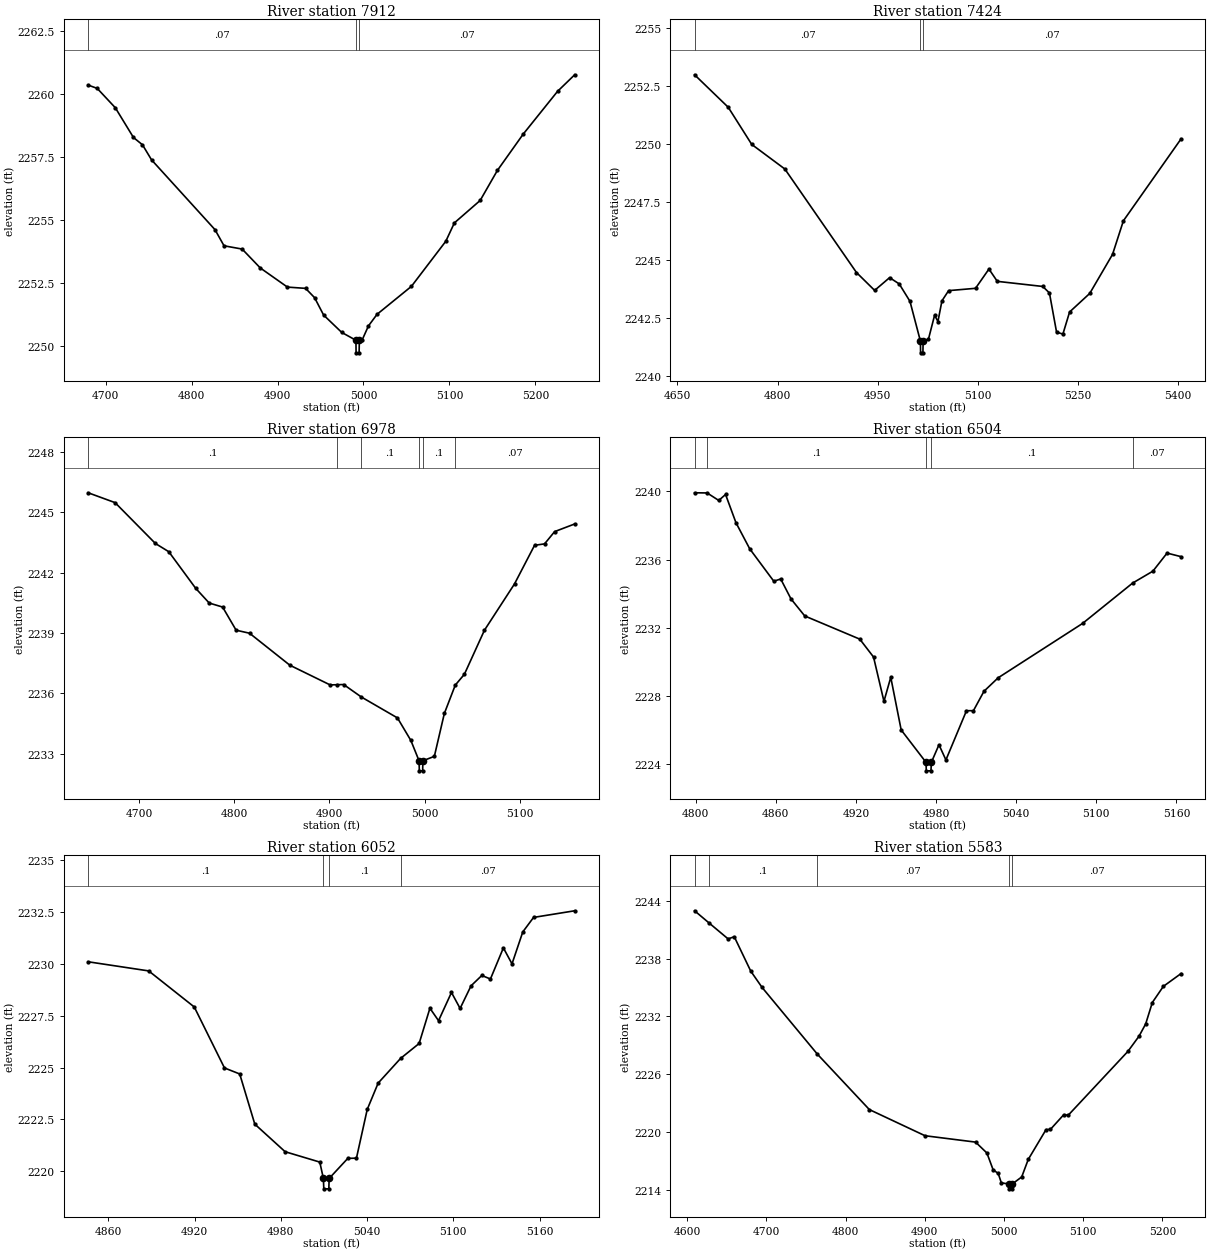
Type RM Length L Ch R = 1,7912,488,488,488
BEGIN DESCRIPTION:
Stream0227 17.0
END DESCRIPTION:
XS GIS Cut Line= 3
      1796875.00     13900424.99      1796775.00     13900125.00
      1796525.01     13900125.00
#Sta/Elev= 30
  4679.6 2260.36  4690.1 2260.23  4711.2 2259.46  4732.3 2258.28  4742.8 2257.99
  4753.4 2257.39  4827.2 2254.62  4837.7 2253.98  4858.8 2253.85  4879.9 2253.10
  4911.5 2252.34  4932.6 2252.29  4943.1 2251.92  4953.6 2251.23  4974.7 2250.54
  4991.2 2250.23  4991.4 2249.73  4994.9 2249.73  4995.2 2250.23  4998.3 2250.23
  5005.8 2250.80  5015.8 2251.26  5055.8 2252.37  5095.8 2254.16  5105.8 2254.89
  5135.8 2255.78  5155.8 2256.97  5185.8 2258.41  5225.8 2260.11  5245.8 2260.77
#Mann=3,-1,0
  4679.6    0.07       0  4991.2    0.05       0  4995.2    0.07       0
Bank Sta=4991.2,4995.2
Exp/Cntr=0.3,0.1

Type RM Length L Ch R = 1,7424,446,446,446
BEGIN DESCRIPTION:
Stream0227 16.0
END DESCRIPTION:
XS GIS Cut Line= 3
      1797124.98     13899874.99      1796875.00     13899675.00
      1796469.14     13899628.07
#Sta/Elev= 30
  4675.8 2252.98  4726.2 2251.58  4761.4 2249.98  4811.0 2248.92  4918.3 2244.46
  4945.5 2243.69  4967.9 2244.24  4982.3 2243.97  4998.4 2243.22  5014.1 2241.50
  5014.3 2241.00  5017.8 2241.00  5018.1 2241.50  5026.1 2241.59  5035.3 2242.62
  5040.3 2242.35  5046.3 2243.24  5056.3 2243.68  5096.6 2243.78  5116.7 2244.61
  5129.2 2244.08  5197.3 2243.86  5207.3 2243.58  5218.0 2241.89  5227.5 2241.81
  5237.5 2242.76  5267.7 2243.56  5301.8 2245.24  5318.1 2246.69  5404.5 2250.22
#Mann=3,-1,0
  4675.8    0.07       0  5014.1    0.05       0  5018.1    0.07       0
Bank Sta=5014.1,5018.1
Exp/Cntr=0.3,0.1

Type RM Length L Ch R = 1,6978,474,474,474
BEGIN DESCRIPTION:
Stream0227 15.0
END DESCRIPTION:
XS GIS Cut Line= 3
      1797174.99     13899524.99      1796925.00     13899275.00
      1796774.96     13899224.99
#Sta/Elev= 30
  4646.2 2245.97  4674.5 2245.48  4716.9 2243.45  4731.0 2243.04  4759.3 2241.22
  4773.5 2240.49  4787.6 2240.29  4801.8 2239.14  4815.9 2238.99  4858.3 2237.40
  4900.7 2236.42  4907.6 2236.43  4914.9 2236.44  4933.5 2235.82  4971.5 2234.78
  4985.6 2233.66  4994.2 2232.65  4994.5 2232.15  4998.0 2232.15  4998.2 2232.65
  5010.3 2232.87  5020.8 2235.00  5032.3 2236.41  5041.9 2236.95  5063.0 2239.14
  5094.6 2241.44  5115.7 2243.36  5126.2 2243.43  5136.8 2244.04  5157.9 2244.42
#Mann=6,-1,0
  4646.2     0.1       0  4907.6    0.07       0  4933.5     0.1       0
  4994.2    0.05       0  4998.2     0.1       0  5032.3    0.07       0
Bank Sta=4994.2,4998.2
Exp/Cntr=0.3,0.1

Type RM Length L Ch R = 1,6504,452,452,452
BEGIN DESCRIPTION:
Stream0227 14.0
END DESCRIPTION:
XS GIS Cut Line= 3
      1797225.03     13898925.01      1797025.00     13898875.00
      1796875.00     13898925.00
#Sta/Elev= 30
  4799.2 2239.92  4808.6 2239.91  4817.3 2239.47  4822.4 2239.82  4830.2 2238.16
  4840.5 2236.63  4858.5 2234.73  4863.7 2234.86  4871.4 2233.69  4881.7 2232.69
  4922.9 2231.33  4933.2 2230.28  4941.0 2227.68  4946.1 2229.09  4953.9 2226.00
  4972.5 2224.10  4972.7 2223.60  4976.2 2223.60  4976.5 2224.10  4982.2 2225.13
  4987.4 2224.24  5002.8 2227.13  5008.0 2227.13  5015.9 2228.27  5026.5 2229.06
  5089.7 2232.25  5127.2 2234.62  5142.4 2235.32  5153.0 2236.38  5163.5 2236.17
#Mann=5,-1,0
  4799.2    0.07       0  4808.6     0.1       0  4972.5    0.05       0
  4976.5     0.1       0  5127.2    0.07       0
Bank Sta=4972.5,4976.5
Exp/Cntr=0.3,0.1

Type RM Length L Ch R = 1,6052,469,469,469
BEGIN DESCRIPTION:
Stream0227 13.0
END DESCRIPTION:
XS GIS Cut Line= 3
      1797174.98     13898474.99      1797025.00     13898425.00
      1796874.97     13898525.02
#Sta/Elev= 30
  4846.0 2230.10  4888.1 2229.66  4919.8 2227.92  4940.8 2224.98  4951.4 2224.69
  4961.9 2222.27  4983.0 2220.94  5007.1 2220.44  5009.6 2219.65  5009.9 2219.15
  5013.4 2219.15  5013.6 2219.65  5026.6 2220.62  5032.6 2220.63  5040.1 2222.98
  5047.7 2224.25  5063.3 2225.44  5076.2 2226.16  5083.7 2227.86  5089.7 2227.26
  5098.7 2228.62  5104.7 2227.85  5112.3 2228.94  5119.8 2229.44  5125.8 2229.27
  5134.8 2230.77  5140.8 2230.00  5148.3 2231.54  5155.8 2232.24  5184.4 2232.56
#Mann=4,-1,0
  4846.0     0.1       0  5009.6    0.05       0  5013.6     0.1       0
  5063.3    0.07       0
Bank Sta=5009.6,5013.6
Exp/Cntr=0.3,0.1

Type RM Length L Ch R = 1,5583,469,469,469
BEGIN DESCRIPTION:
Stream0227 12.0
END DESCRIPTION:
XS GIS Cut Line= 3
      1797524.99     13898274.99      1797225.00     13898025.00
      1797025.00     13897925.00
#Sta/Elev= 30
  4609.5 2242.95  4627.3 2241.72  4651.8 2240.04  4659.6 2240.26  4680.4 2236.70
  4694.7 2235.01  4764.5 2228.10  4830.1 2222.36  4900.4 2219.65  4964.2 2218.99
  4978.5 2217.86  4986.3 2216.13  4992.8 2215.74  4996.7 2214.77  5006.4 2214.65
  5006.6 2214.15  5010.1 2214.15  5010.4 2214.65  5022.4 2215.38  5030.7 2217.20
  5053.1 2220.28  5058.7 2220.31  5075.5 2221.83  5081.1 2221.77  5156.5 2228.39
  5170.5 2229.96  5178.9 2231.23  5187.3 2233.45  5201.2 2235.12  5223.6 2236.45
#Mann=5,-1,0
  4609.5    0.07       0  4627.3     0.1       0  4764.5    0.07       0
  5006.4    0.05       0  5010.4    0.07       0
Bank Sta=5006.4,5010.4
Exp/Cntr=0.3,0.1

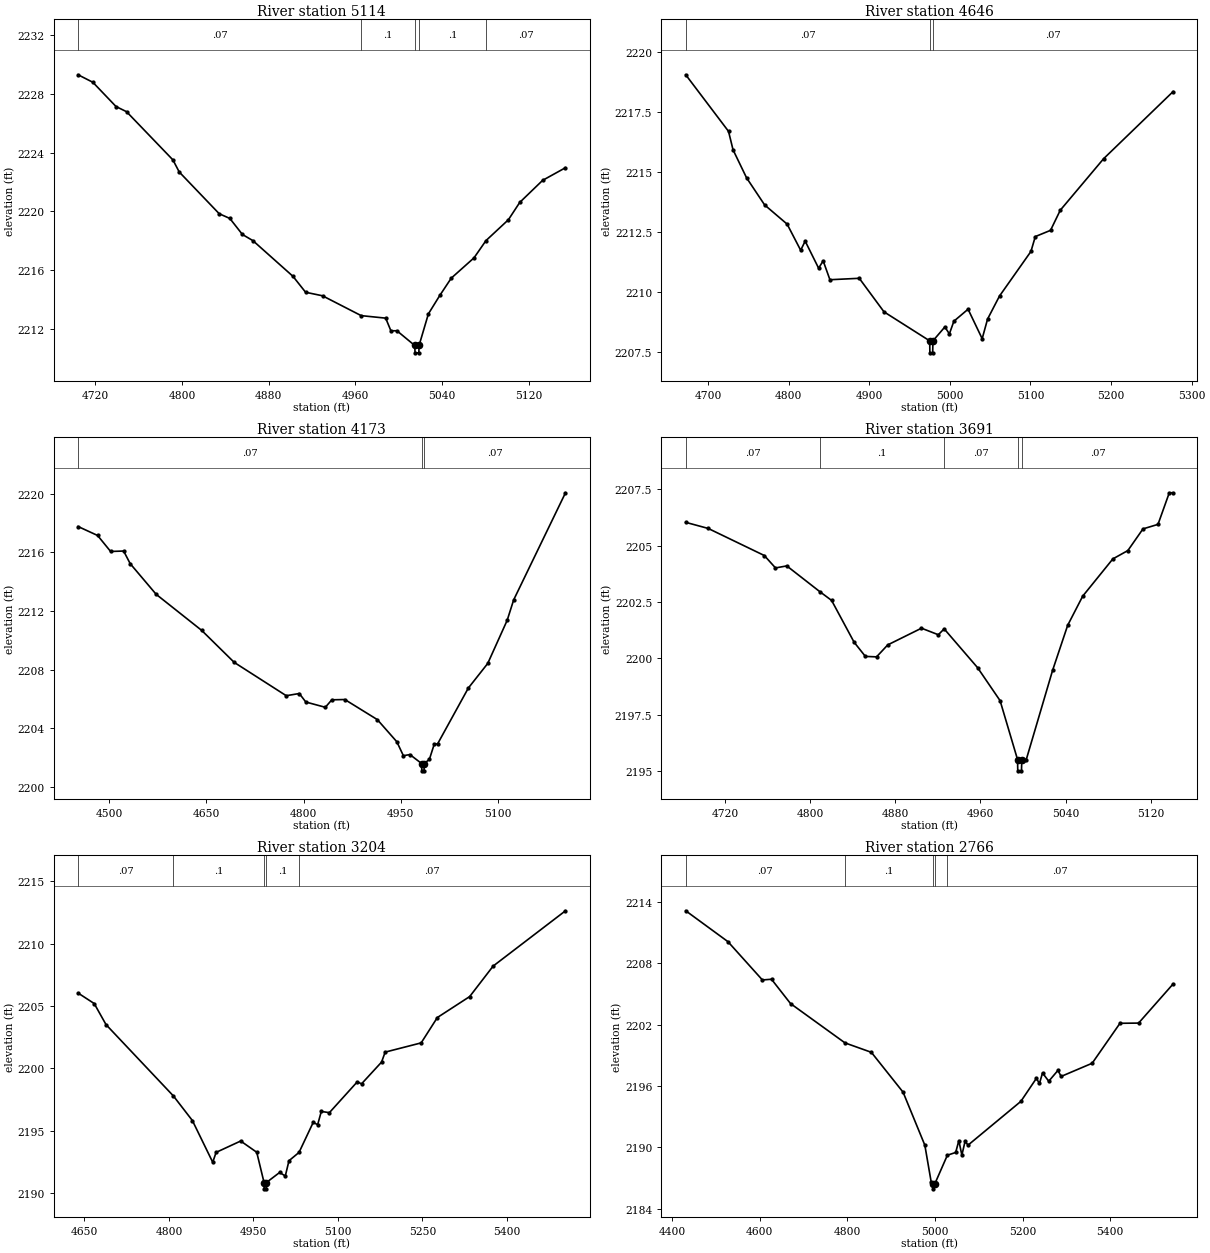
Type RM Length L Ch R = 1,5114,468,468,468
BEGIN DESCRIPTION:
Stream0227 11.0
END DESCRIPTION:
XS GIS Cut Line= 3
      1797575.01     13897875.01      1797425.00     13897625.00
      1797274.97     13897574.99
#Sta/Elev= 30
  4704.1 2229.29  4717.7 2228.78  4739.1 2227.13  4748.8 2226.78  4791.6 2223.50
  4797.4 2222.68  4834.3 2219.84  4844.1 2219.52  4855.7 2218.43  4865.4 2218.01
  4902.4 2215.58  4914.0 2214.50  4929.6 2214.26  4965.3 2212.91  4987.9 2212.74
  4992.7 2211.88  4998.3 2211.88  5014.7 2210.88  5015.0 2210.38  5018.5 2210.38
  5018.7 2210.88  5027.3 2213.03  5037.8 2214.28  5048.4 2215.46  5069.4 2216.84
  5080.4 2218.01  5101.1 2219.43  5111.6 2220.61  5132.7 2222.11  5153.8 2222.97
#Mann=5,-1,0
  4704.1    0.07       0  4965.3     0.1       0  5014.7    0.05       0
  5018.7     0.1       0  5080.4    0.07       0
Bank Sta=5014.7,5018.7
Exp/Cntr=0.3,0.1

Type RM Length L Ch R = 1,4646,473,473,473
BEGIN DESCRIPTION:
Stream0227 10.0
END DESCRIPTION:
XS GIS Cut Line= 3
      1797825.03     13897375.02      1797525.00     13897225.00
      1797275.00     13897325.00
#Sta/Elev= 30
  4672.3 2219.05  4725.4 2216.69  4731.0 2215.92  4747.8 2214.75  4770.2 2213.62
  4798.1 2212.82  4814.9 2211.73  4820.5 2212.11  4837.2 2210.98  4842.8 2211.29
  4851.2 2210.50  4887.6 2210.56  4918.3 2209.16  4975.0 2207.95  4975.2 2207.45
  4978.7 2207.45  4979.0 2207.95  4993.8 2208.53  4999.4 2208.24  5005.0 2208.77
  5022.6 2209.27  5040.1 2208.04  5046.8 2208.86  5061.6 2209.82  5100.6 2211.68
  5106.0 2212.30  5124.9 2212.56  5137.0 2213.40  5190.8 2215.55  5277.0 2218.35
#Mann=3,-1,0
  4672.3    0.07       0  4975.0    0.05       0  4979.0    0.07       0
Bank Sta=4975,4979
Exp/Cntr=0.3,0.1

Type RM Length L Ch R = 1,4173,482,482,482
BEGIN DESCRIPTION:
Stream0227 9.0
END DESCRIPTION:
XS GIS Cut Line= 3
      1797875.02     13896775.00      1797325.00     13896825.00
      1797124.99     13896825.00
#Sta/Elev= 30
  4451.9 2217.75  4482.0 2217.14  4502.1 2216.05  4522.2 2216.08  4532.3 2215.22
  4572.4 2213.13  4642.7 2210.67  4692.9 2208.49  4773.2 2206.22  4793.3 2206.37
  4803.4 2205.79  4833.5 2205.43  4843.5 2205.94  4863.6 2205.96  4913.8 2204.59
  4943.9 2203.08  4954.0 2202.13  4964.0 2202.21  4982.1 2201.60  4982.4 2201.10
  4985.9 2201.10  4986.1 2201.60  4994.1 2201.88  5001.7 2202.93  5006.7 2202.93
  5054.2 2206.74  5084.2 2208.42  5114.2 2211.36  5124.2 2212.75  5204.2 2220.05
#Mann=3,-1,0
  4451.9    0.07       0  4982.1    0.05       0  4986.1    0.07       0
Bank Sta=4982.1,4986.1
Exp/Cntr=0.3,0.1

Type RM Length L Ch R = 1,3691,487,487,487
BEGIN DESCRIPTION:
Stream0227 8.0
END DESCRIPTION:
XS GIS Cut Line= 3
      1797525.01     13896475.00      1797225.00     13896375.00
      1797124.97     13896475.03
#Sta/Elev= 30
  4683.2 2206.03  4704.3 2205.76  4757.0 2204.56  4767.5 2204.01  4778.1 2204.10
  4809.1 2202.96  4820.2 2202.57  4841.3 2200.72  4851.9 2200.09  4862.4 2200.07
  4872.9 2200.60  4904.6 2201.34  4920.4 2201.05  4925.9 2201.31  4957.3 2199.59
  4978.4 2198.13  4994.8 2195.52  4995.0 2195.02  4998.5 2195.02  4998.8 2195.52
  5003.0 2195.52  5027.7 2199.47  5041.9 2201.47  5056.0 2202.76  5084.3 2204.41
  5098.4 2204.78  5112.6 2205.74  5126.7 2205.94  5137.3 2207.34  5140.9 2207.34
#Mann=5,-1,0
  4683.2    0.07       0  4809.1     0.1       0  4925.9    0.07       0
  4994.8    0.05       0  4998.8    0.07       0
Bank Sta=4994.8,4998.8
Exp/Cntr=0.3,0.1

Type RM Length L Ch R = 1,3204,438,438,438
BEGIN DESCRIPTION:
Stream0227 7.0
END DESCRIPTION:
XS GIS Cut Line= 3
      1797425.01     13895725.00      1797125.00     13895925.00
      1796804.49     13896314.40
#Sta/Elev= 30
  4638.9 2206.04  4667.5 2205.20  4688.5 2203.51  4808.0 2197.80  4841.7 2195.83
  4877.8 2192.49  4883.8 2193.28  4927.4 2194.19  4955.9 2193.29  4968.9 2190.86
  4969.2 2190.36  4972.7 2190.36  4972.9 2190.86  4996.5 2191.67  5006.6 2191.39
  5013.1 2192.61  5031.0 2193.28  5056.1 2195.68  5064.0 2195.50  5070.5 2196.56
  5084.8 2196.46  5134.3 2198.93  5141.9 2198.77  5177.4 2200.51  5183.8 2201.31
  5247.7 2202.05  5276.4 2204.08  5333.8 2205.76  5375.4 2208.20  5503.8 2212.63
#Mann=5,-1,0
  4638.9    0.07       0  4808.0     0.1       0  4968.9    0.05       0
  4972.9     0.1       0  5031.0    0.07       0
Bank Sta=4968.9,4972.9
Exp/Cntr=0.3,0.1

Type RM Length L Ch R = 1,2766,465,465,465
BEGIN DESCRIPTION:
Stream0227 6.0
END DESCRIPTION:
XS GIS Cut Line= 3
      1797427.46     13895221.97      1796975.00     13895575.00
      1796605.21     13895966.61
#Sta/Elev= 30
  4431.0 2213.14  4527.3 2210.12  4606.0 2206.37  4626.8 2206.44  4670.2 2204.06
  4794.6 2200.21  4854.7 2199.29  4927.1 2195.39  4976.8 2190.20  4991.3 2186.59
  4995.7 2186.43  4995.9 2185.93  4999.7 2186.43  5028.2 2189.22  5047.2 2189.49
  5054.4 2190.65  5061.3 2189.23  5068.6 2190.57  5075.5 2190.21  5196.0 2194.49
  5231.2 2196.73  5238.5 2196.25  5245.4 2197.27  5259.6 2196.46  5280.6 2197.52
  5287.9 2196.93  5358.7 2198.22  5422.2 2202.13  5464.7 2202.15  5543.5 2205.98
#Mann=5,-1,0
  4431.0    0.07       0  4794.6     0.1       0  4995.7    0.05       0
  4999.7     0.1       0  5028.2    0.07       0
Bank Sta=4995.7,4999.7
Exp/Cntr=0.3,0.1

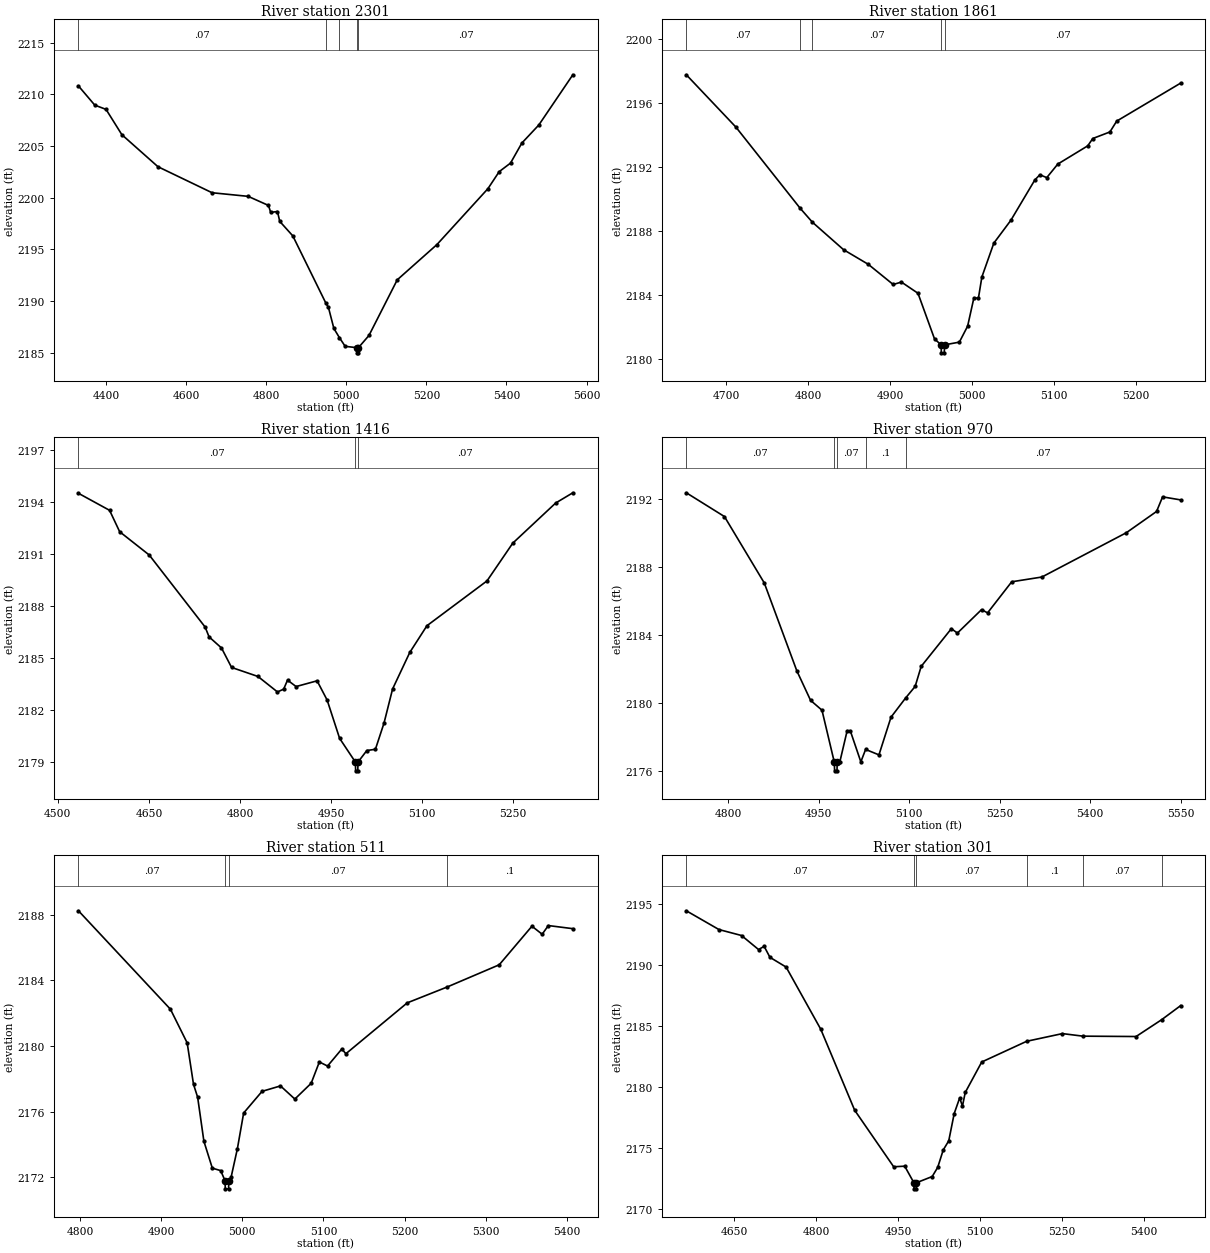
Type RM Length L Ch R = 1,2301,440,440,440
BEGIN DESCRIPTION:
Stream0227 5.0
END DESCRIPTION:
XS GIS Cut Line= 3
      1797276.17     13894981.91      1796675.00     13895275.00
      1796274.99     13895675.01
#Sta/Elev= 30
  4331.2 2210.82  4372.0 2208.96  4400.1 2208.55  4439.6 2206.10  4529.7 2203.00
  4664.9 2200.48  4755.0 2200.13  4805.7 2199.25  4811.2 2198.58  4828.2 2198.66
  4833.8 2197.71  4866.5 2196.30  4948.9 2189.80  4955.5 2189.37  4969.0 2187.34
  4982.7 2186.46  4997.2 2185.61  5026.3 2185.48  5026.5 2184.98  5030.0 2184.98
  5030.3 2185.48  5056.6 2186.66  5127.3 2192.05  5226.3 2195.46  5353.6 2200.87
  5381.8 2202.52  5410.1 2203.35  5438.4 2205.29  5480.8 2207.04  5565.7 2211.90
#Mann=5,-1,0
  4331.2    0.07       0  4948.9     0.1       0  4982.7    0.07       0
  5026.3    0.05       0  5030.3    0.07       0
Bank Sta=5026.3,5030.3
Exp/Cntr=0.3,0.1

Type RM Length L Ch R = 1,1861,445,445,445
BEGIN DESCRIPTION:
Stream0227 4.0
END DESCRIPTION:
XS GIS Cut Line= 3
      1796774.97     13894975.00      1796425.00     13894925.00
      1796225.01     13895074.99
#Sta/Elev= 30
  4651.5 2197.78  4712.1 2194.50  4790.5 2189.42  4805.4 2188.55  4843.4 2186.83
  4873.7 2185.91  4904.0 2184.65  4914.1 2184.80  4934.3 2184.10  4954.5 2181.24
  4962.6 2180.87  4962.8 2180.37  4966.4 2180.37  4966.7 2180.87  4984.8 2181.04
  4994.9 2182.04  5002.5 2183.80  5008.1 2183.80  5012.3 2185.12  5026.9 2187.24
  5047.7 2188.67  5076.9 2191.19  5083.1 2191.52  5091.5 2191.34  5105.0 2192.19
  5141.5 2193.33  5147.7 2193.79  5168.6 2194.20  5176.9 2194.88  5255.0 2197.26
#Mann=5,-1,0
  4651.5    0.07       0  4790.5     0.1       0  4805.4    0.07       0
  4962.6    0.05       0  4966.7    0.07       0
Bank Sta=4962.6,4966.7
Exp/Cntr=0.3,0.1

Type RM Length L Ch R = 1,1416,446,446,446
BEGIN DESCRIPTION:
Stream0227 3.0
END DESCRIPTION:
XS GIS Cut Line= 3
      1796725.05     13894625.01      1796275.00     13894525.00
      1796024.98     13894775.02
#Sta/Elev= 30
  4533.9 2194.49  4585.2 2193.51  4601.8 2192.28  4650.5 2190.94  4742.7 2186.79
  4749.1 2186.23  4769.6 2185.59  4786.2 2184.47  4829.7 2183.95  4861.8 2183.06
  4872.0 2183.22  4878.4 2183.74  4892.5 2183.37  4927.1 2183.70  4943.7 2182.59
  4964.2 2180.39  4990.3 2179.02  4990.6 2178.52  4994.2 2178.52  4994.4 2179.02
  5009.1 2179.69  5023.2 2179.76  5037.4 2181.27  5051.5 2183.23  5079.8 2185.33
  5108.1 2186.87  5207.1 2189.45  5249.5 2191.62  5320.2 2193.93  5348.5 2194.52
#Mann=3,-1,0
  4533.9    0.07       0  4990.3    0.05       0  4994.4    0.07       0
Bank Sta=4990.3,4994.4
Exp/Cntr=0.3,0.1

Type RM Length L Ch R = 1,970,459,459,459
BEGIN DESCRIPTION:
Stream0227 2.0
END DESCRIPTION:
XS GIS Cut Line= 3
      1796724.96     13894324.99      1796475.00     13894225.00
      1795925.02     13894225.00
#Sta/Elev= 30
  4730.8 2192.36  4794.0 2190.96  4860.0 2187.05  4913.9 2181.88  4936.7 2180.14
  4955.6 2179.56  4976.1 2176.49  4976.5 2175.99  4980.5 2175.99  4980.8 2176.49
  4985.2 2176.52  4997.3 2178.35  5002.5 2178.35  5020.0 2176.52  5027.9 2177.25
  5050.0 2176.93  5070.0 2179.15  5094.0 2180.27  5110.0 2180.96  5120.0 2182.14
  5170.0 2184.36  5180.0 2184.10  5220.0 2185.48  5230.0 2185.29  5270.0 2187.12
  5320.0 2187.40  5460.0 2190.01  5510.0 2191.26  5520.0 2192.12  5550.0 2191.94
#Mann=5,-1,0
  4730.8    0.07       0  4976.1    0.05       0  4980.8    0.07       0
  5027.9     0.1       0  5094.0    0.07       0
Bank Sta=4976.1,4980.8
Exp/Cntr=0.3,0.1

Type RM Length L Ch R = 1,511,210,210,210
BEGIN DESCRIPTION:
Stream0227 1.0
END DESCRIPTION:
XS GIS Cut Line= 3
      1796825.03     13893875.01      1796625.00     13893825.00
      1796225.00     13893875.00
#Sta/Elev= 30
  4798.0 2188.24  4911.4 2182.24  4932.0 2180.19  4939.8 2177.67  4944.9 2176.88
  4952.6 2174.20  4963.0 2172.56  4973.3 2172.41  4978.6 2171.80  4979.0 2171.30
  4983.0 2171.30  4983.3 2171.80  4986.1 2172.00  4993.9 2173.75  5001.6 2175.92
  5024.3 2177.24  5047.0 2177.57  5064.7 2176.77  5084.8 2177.73  5094.9 2179.03
  5105.0 2178.78  5122.6 2179.82  5127.6 2179.53  5203.2 2182.63  5252.1 2183.59
  5316.6 2184.95  5356.9 2187.30  5369.5 2186.81  5377.1 2187.34  5407.3 2187.15
#Mann=4,-1,0
  4798.0    0.07       0  4978.6    0.05       0  4983.3    0.07       0
  5252.1     0.1       0
Bank Sta=4978.6,4983.3
Exp/Cntr=0.3,0.1

Type RM Length L Ch R = 1,301,0,0,0
BEGIN DESCRIPTION:
Stream0227 0.0
END DESCRIPTION:
XS GIS Cut Line= 4
      1797102.65     13893708.44      1796773.67     13893620.01
      1796447.52     13893659.89      1796269.91     13893814.94
#Sta/Elev= 30
  4562.0 2194.46  4621.7 2192.92  4663.1 2192.43  4694.2 2191.28  4704.5 2191.54
  4715.1 2190.64  4744.7 2189.84  4808.1 2184.74  4870.2 2178.09  4941.6 2173.45
  4961.8 2173.50  4978.6 2172.14  4978.9 2171.64  4983.0 2171.64  4983.3 2172.14
  5012.1 2172.65  5022.2 2173.40  5032.3 2174.83  5042.4 2175.58  5052.4 2177.82
  5062.4 2179.10  5067.5 2178.43  5072.6 2179.55  5102.8 2182.05  5185.1 2183.75
  5250.5 2184.38  5288.1 2184.17  5385.3 2184.14  5432.1 2185.52  5467.0 2186.68
#Mann=6,-1,0
  4562.0    0.07       0  4978.6    0.05       0  4983.3    0.07       0
  5185.1     0.1       0  5288.1    0.07       0  5432.1     0.1       0
Bank Sta=4978.6,4983.3
Exp/Cntr=0.3,0.1

Chan Stop Cuts=-1