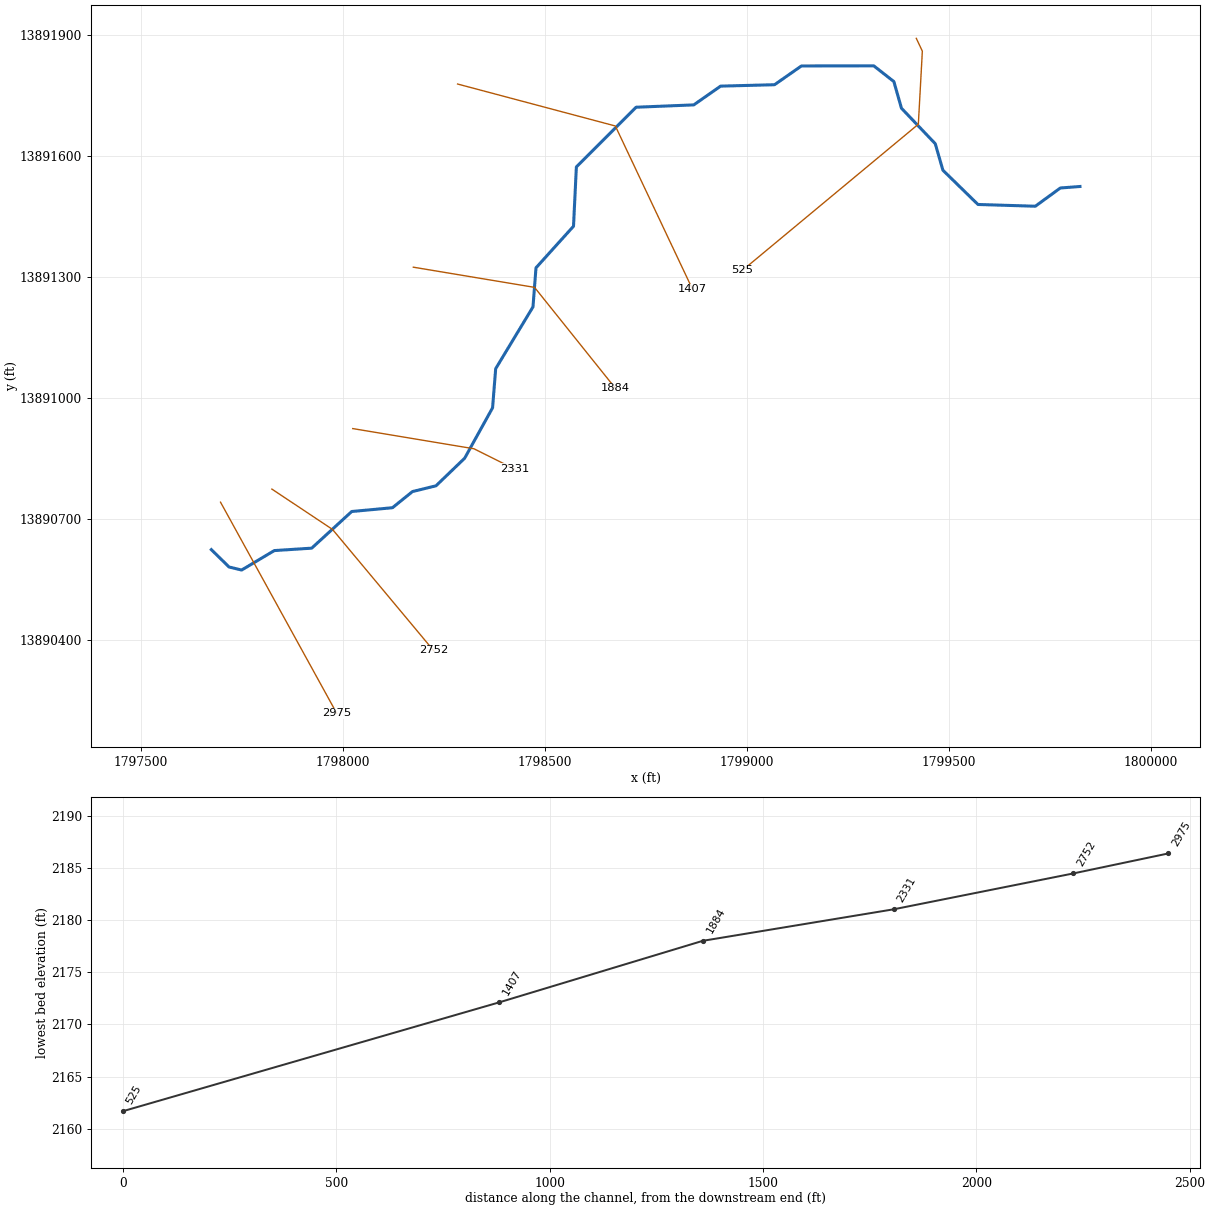
--- Stream0228.prj (project) ---

Proj Title=Stream0228 Base Level Engineering
Current Plan=p01
Default Exp/Contr=0.3,0.1
English Units
Geom File=g01
Flow File=f01
Plan File=p01
BEGIN DESCRIPTION:
Stream0228
END DESCRIPTION:

--- Stream0228.p01 (plan) ---

Plan Title=Multiple Run
Short Identifier=Multiple
Geom File=g01
Flow File=f01
Subcritical Flow
K Sum by GR= 0
Std Step Tol= 0.01
Critical Tol= 0.01
Num of Std Step Trials= 20
Max Error Tol= 0.3
Flow Tol Ratio= 0.001
Split Flow NTrial= 30
Split Flow Tol= 0.02
Split Flow Ratio= 0.02
Log Output Level= 0
Friction Slope Method= 1
Unsteady Friction Slope Method= 2
Unsteady Bridges Friction Slope Method= 1
Parabolic Critical Depth
Global Vel Dist=  1 , 1 , 1
Global Log Level= 0
CheckData=True
Encroach Param= -1, 0, 0, 0
BEGIN DESCRIPTION:
Multiple Run
END DESCRIPTION:

--- Stream0228.f01 (steady flow) ---

Flow Title=Multiple
Number of Profiles=7
Profile Names=10-year,25-year,50-year,1pct_min,100-year,1pct_plu,500-year
River Rch & RM= Stream0228,Reach-1,2975
     712    1183    1619    1073    2140    4270    3693
Boundary for River Rch & Prof#=Stream0228,Reach-1,1
Up Type=0
Dn Type=3
Dn Slope=0.005
Boundary for River Rch & Prof#=Stream0228,Reach-1,2
Up Type=0
Dn Type=3
Dn Slope=0.005
Boundary for River Rch & Prof#=Stream0228,Reach-1,3
Up Type=0
Dn Type=3
Dn Slope=0.005
Boundary for River Rch & Prof#=Stream0228,Reach-1,4
Up Type=0
Dn Type=3
Dn Slope=0.005
Boundary for River Rch & Prof#=Stream0228,Reach-1,5
Up Type=0
Dn Type=3
Dn Slope=0.005
Boundary for River Rch & Prof#=Stream0228,Reach-1,6
Up Type=0
Dn Type=3
Dn Slope=0.005
Boundary for River Rch & Prof#=Stream0228,Reach-1,7
Up Type=0
Dn Type=3
Dn Slope=0.005

--- Stream0228.g01 (geometry) ---

Geom Title=Existing Conditions

River Reach=Stream0228,Reach-1
Reach XY= 30
      1797675.00     13890625.00      1797718.85     13890581.95
      1797750.05     13890574.39      1797830.96     13890622.63
      1797923.50     13890628.62      1798022.58     13890719.46
      1798123.41     13890728.83      1798172.83     13890768.86
      1798231.07     13890783.13      1798302.01     13890851.48
      1798371.17     13890976.58      1798378.83     13891073.42
      1798471.17     13891226.59      1798478.62     13891323.50
      1798571.44     13891426.47      1798578.54     13891573.53
      1798726.47     13891721.46      1798869.06     13891727.27
      1798935.51     13891773.77      1799069.06     13891777.27
      1799135.51     13891823.78      1799314.72     13891824.02
      1799364.38     13891785.06      1799383.19     13891718.98
      1799466.82     13891631.04      1799485.77     13891565.30
      1799572.54     13891480.45      1799714.53     13891476.10
      1799776.51     13891521.35      1799825.00     13891525.00

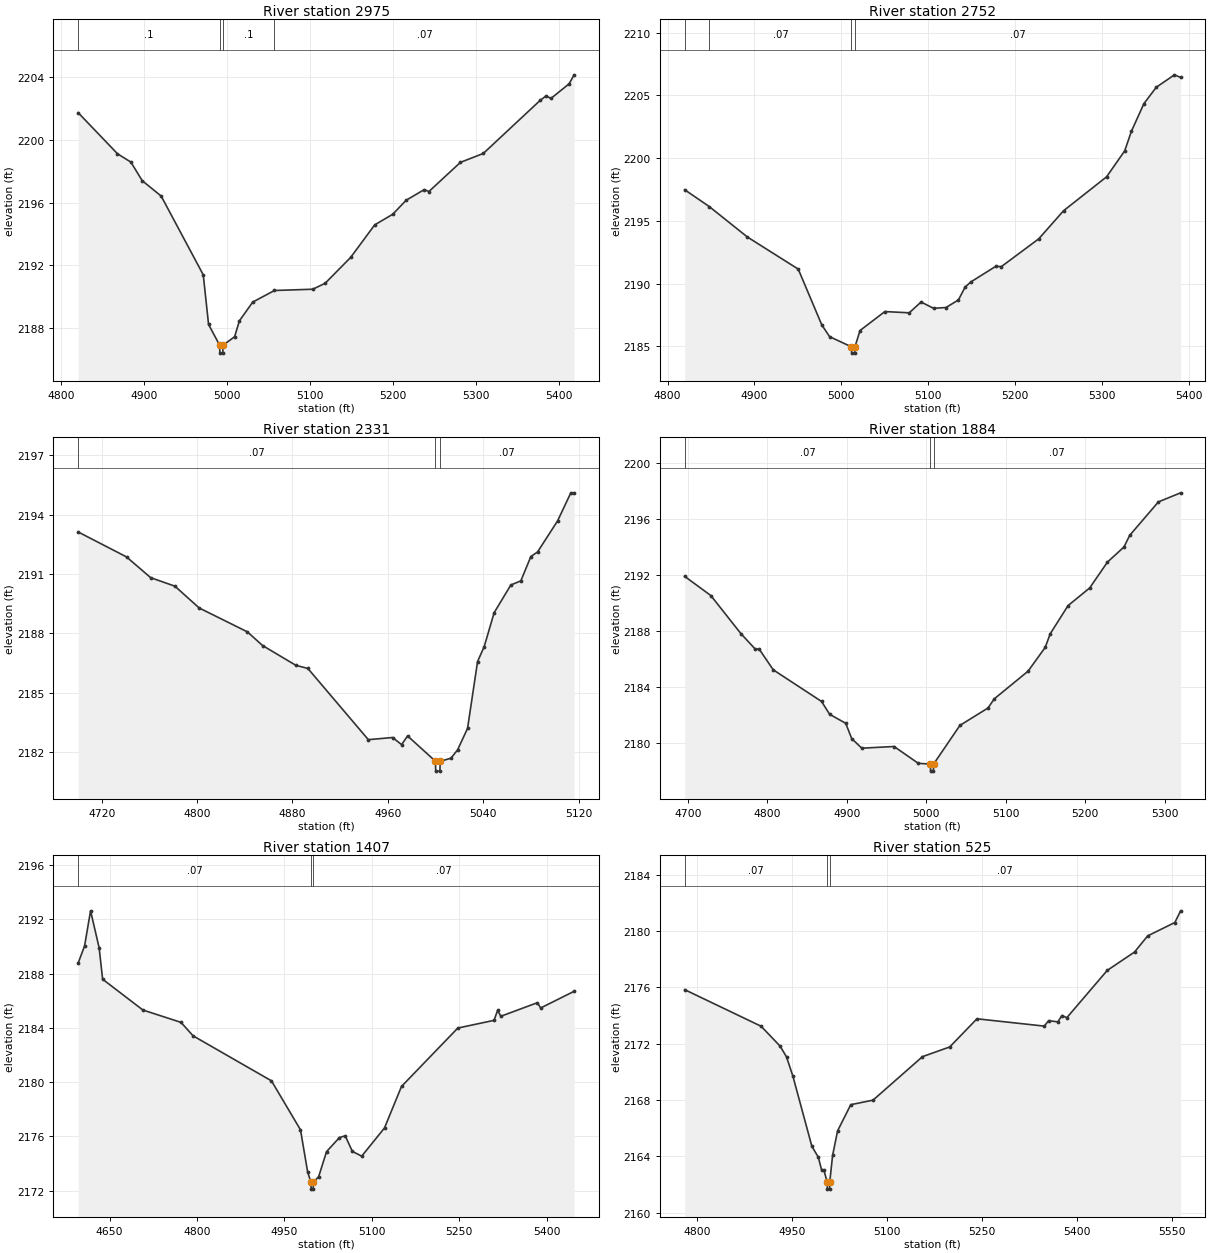
Type RM Length L Ch R = 1,2975,223,223,223
BEGIN DESCRIPTION:
Stream0228 6.0
END DESCRIPTION:
XS GIS Cut Line= 2
      1797697.81     13890742.56      1797985.53     13890219.12
#Sta/Elev= 30
  4820.6 2201.74  4867.9 2199.12  4884.0 2198.59  4897.7 2197.40  4920.5 2196.42
  4971.2 2191.39  4977.6 2188.22  4991.0 2186.89  4991.2 2186.39  4994.7 2186.39
  4995.0 2186.89  5009.0 2187.44  5014.7 2188.45  5030.8 2189.65  5057.0 2190.39
  5103.1 2190.47  5118.0 2190.85  5148.7 2192.50  5177.7 2194.58  5199.5 2195.26
  5215.5 2196.15  5237.3 2196.83  5243.0 2196.71  5280.9 2198.57  5308.5 2199.14
  5377.0 2202.53  5384.2 2202.82  5389.9 2202.65  5411.7 2203.58  5417.9 2204.16
#Mann=4,-1,0
  4820.6     0.1       0  4991.0    0.05       0  4995.0     0.1       0
  5057.0    0.07       0
Bank Sta=4991,4995
Exp/Cntr=0.3,0.1

Type RM Length L Ch R = 1,2752,421,421,421
BEGIN DESCRIPTION:
Stream0228 5.0
END DESCRIPTION:
XS GIS Cut Line= 3
      1797824.97     13890775.02      1797975.00     13890675.00
      1798224.98     13890375.02
#Sta/Elev= 30
  4819.7 2197.48  4848.0 2196.14  4891.8 2193.72  4950.4 2191.16  4977.5 2186.72
  4986.5 2185.78  5011.7 2184.97  5011.9 2184.47  5015.4 2184.47  5015.7 2184.97
  5021.5 2186.27  5050.1 2187.78  5078.1 2187.68  5091.8 2188.54  5106.1 2188.04
  5120.4 2188.10  5134.7 2188.70  5142.5 2189.73  5149.1 2190.14  5177.7 2191.38
  5184.2 2191.36  5227.2 2193.57  5255.8 2195.81  5305.3 2198.51  5326.1 2200.57
  5333.9 2202.14  5348.2 2204.33  5362.5 2205.64  5383.4 2206.63  5390.5 2206.42
#Mann=4,-1,0
  4819.7     0.1       0  4848.0    0.07       0  5011.7    0.05       0
  5015.7    0.07       0
Bank Sta=5011.7,5015.7
Exp/Cntr=0.3,0.1

Type RM Length L Ch R = 1,2331,447,447,447
BEGIN DESCRIPTION:
Stream0228 4.0
END DESCRIPTION:
XS GIS Cut Line= 3
      1798025.01     13890925.00      1798325.00     13890875.00
      1798424.97     13890825.01
#Sta/Elev= 30
  4700.3 2193.12  4740.8 2191.86  4761.1 2190.81  4781.4 2190.38  4801.7 2189.28
  4842.2 2188.07  4854.9 2187.38  4882.8 2186.38  4892.9 2186.22  4943.6 2182.62
  4963.9 2182.73  4971.5 2182.37  4976.5 2182.81  4999.9 2181.53  5000.1 2181.03
  5003.6 2181.03  5003.9 2181.53  5012.8 2181.68  5018.4 2182.10  5026.8 2183.19
  5035.2 2186.57  5040.8 2187.33  5049.1 2189.04  5063.1 2190.44  5071.5 2190.65
  5079.9 2191.88  5085.5 2192.11  5102.3 2193.68  5113.4 2195.10  5116.2 2195.10
#Mann=3,-1,0
  4700.3    0.07       0  4999.9    0.05       0  5003.9    0.07       0
Bank Sta=4999.9,5003.9
Exp/Cntr=0.3,0.1

Type RM Length L Ch R = 1,1884,477,477,477
BEGIN DESCRIPTION:
Stream0228 3.0
END DESCRIPTION:
XS GIS Cut Line= 3
      1798175.02     13891325.00      1798475.00     13891275.00
      1798675.02     13891024.98
#Sta/Elev= 30
  4695.9 2191.93  4728.8 2190.56  4766.8 2187.83  4784.6 2186.74  4789.7 2186.73
  4807.4 2185.25  4868.2 2182.99  4878.4 2182.07  4898.6 2181.43  4906.2 2180.33
  4918.9 2179.65  4959.5 2179.77  4989.9 2178.57  5005.2 2178.51  5005.5 2178.01
  5009.0 2178.01  5009.2 2178.51  5042.4 2181.28  5077.7 2182.52  5085.7 2183.18
  5128.1 2185.15  5149.7 2186.85  5156.1 2187.83  5178.5 2189.84  5205.7 2191.10
  5228.1 2192.95  5248.9 2194.03  5256.1 2194.86  5292.2 2197.25  5320.2 2197.90
#Mann=3,-1,0
  4695.9    0.07       0  5005.2    0.05       0  5009.2    0.07       0
Bank Sta=5005.2,5009.2
Exp/Cntr=0.3,0.1

Type RM Length L Ch R = 1,1407,882,882,882
BEGIN DESCRIPTION:
Stream0228 2.0
END DESCRIPTION:
XS GIS Cut Line= 3
      1798284.51     13891779.02      1798675.00     13891675.00
      1798865.82     13891270.68
#Sta/Elev= 30
  4596.2 2188.78  4607.1 2190.03  4617.4 2192.62  4632.1 2189.90  4638.1 2187.58
  4707.2 2185.31  4772.6 2184.40  4793.3 2183.41  4927.9 2180.09  4977.7 2176.48
  4990.0 2173.37  4995.7 2172.61  4996.0 2172.11  4999.5 2172.11  4999.7 2172.61
  5008.9 2173.03  5022.4 2174.87  5044.5 2175.91  5054.5 2176.04  5066.7 2174.89
  5082.8 2174.54  5121.9 2176.62  5151.1 2179.68  5247.7 2183.98  5309.9 2184.55
  5316.0 2185.28  5321.6 2184.85  5384.4 2185.85  5389.9 2185.46  5447.4 2186.69
#Mann=3,-1,0
  4596.2    0.07       0  4995.7    0.05       0  4999.7    0.07       0
Bank Sta=4995.7,4999.7
Exp/Cntr=0.3,0.1

Type RM Length L Ch R = 1,525,0,0,0
BEGIN DESCRIPTION:
Stream0228 1.0
END DESCRIPTION:
XS GIS Cut Line= 4
      1799419.90     13891892.23      1799434.86     13891860.41
      1799424.98     13891679.33      1798989.53     13891317.13
#Sta/Elev= 30
  4780.4 2175.84  4901.1 2173.24  4931.2 2171.82  4941.2 2171.06  4951.2 2169.70
  4981.2 2164.71  4991.2 2163.95  4996.6 2163.03  5000.1 2163.03  5005.4 2162.17
  5005.7 2161.67  5009.2 2161.67  5009.4 2162.17  5013.9 2164.06  5021.8 2165.81
  5042.6 2167.67  5077.7 2167.99  5155.8 2171.08  5198.8 2171.77  5241.8 2173.77
  5348.1 2173.25  5355.0 2173.64  5369.4 2173.55  5375.9 2174.00  5383.7 2173.85
  5447.5 2177.21  5490.5 2178.51  5511.3 2179.66  5554.2 2180.61  5563.3 2181.44
#Mann=3,-1,0
  4780.4    0.07       0  5005.4    0.05       0  5009.4    0.07       0
Bank Sta=5005.4,5009.4
Exp/Cntr=0.3,0.1

Chan Stop Cuts=-1