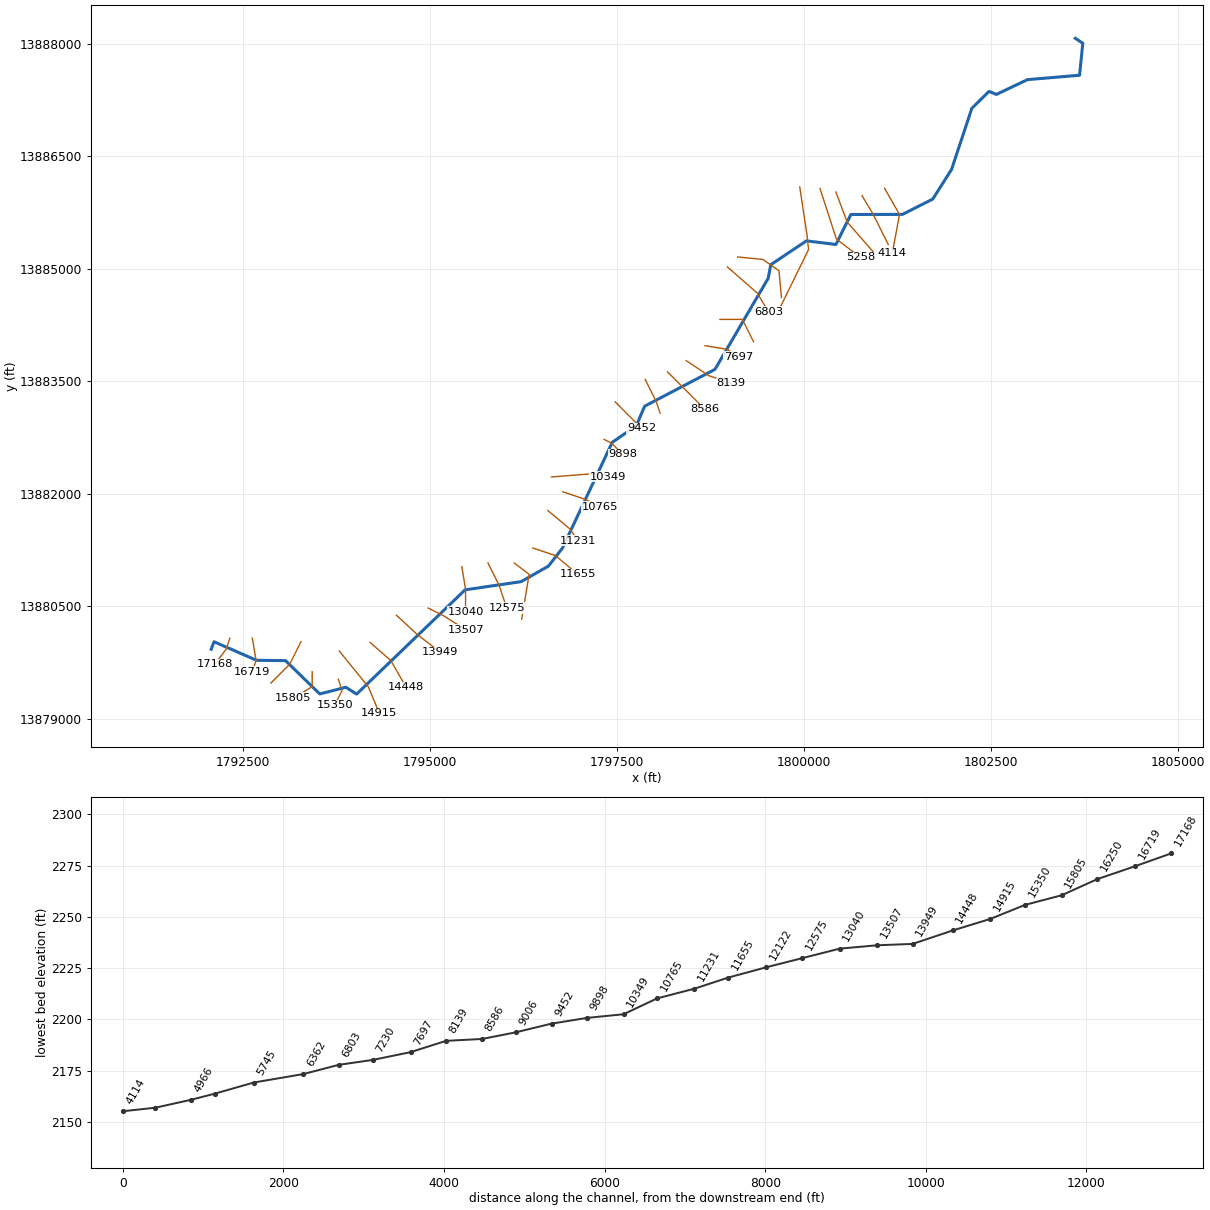
--- Stream0229.prj (project) ---

Proj Title=Stream0229 Base Level Engineering
Current Plan=p01
Default Exp/Contr=0.3,0.1
English Units
Geom File=g01
Flow File=f01
Plan File=p01
BEGIN DESCRIPTION:
Stream0229
END DESCRIPTION:

--- Stream0229.p01 (plan) ---

Plan Title=Multiple Run
Short Identifier=Multiple
Geom File=g01
Flow File=f01
Subcritical Flow
K Sum by GR= 0
Std Step Tol= 0.01
Critical Tol= 0.01
Num of Std Step Trials= 20
Max Error Tol= 0.3
Flow Tol Ratio= 0.001
Split Flow NTrial= 30
Split Flow Tol= 0.02
Split Flow Ratio= 0.02
Log Output Level= 0
Friction Slope Method= 1
Unsteady Friction Slope Method= 2
Unsteady Bridges Friction Slope Method= 1
Parabolic Critical Depth
Global Vel Dist=  1 , 1 , 1
Global Log Level= 0
CheckData=True
Encroach Param= -1, 0, 0, 0
BEGIN DESCRIPTION:
Multiple Run
END DESCRIPTION:

--- Stream0229.f01 (steady flow) ---

Flow Title=Multiple
Number of Profiles=7
Profile Names=10-year,25-year,50-year,1pct_min,100-year,1pct_plu,500-year
River Rch & RM= Stream0229,Reach-1,17168
     389     616     818     526    1050    2096    1708
River Rch & RM= Stream0229,Reach-1,15350
    1009    1695    2337    1556    3105    6195    5417
River Rch & RM= Stream0229,Reach-1,6803
    1521    2629    3692    2500    4989    9954    9014
River Rch & RM= Stream0229,Reach-1,4517
    2378    4198    5979    4100    8180   16321   15160
River Rch & RM= Stream0229,Reach-1,3640
    2581    4565    6511    4470    8918   17794   16564
Boundary for River Rch & Prof#=Stream0229,Reach-1,1
Up Type=0
Dn Type=3
Dn Slope=0.005
Boundary for River Rch & Prof#=Stream0229,Reach-1,2
Up Type=0
Dn Type=3
Dn Slope=0.005
Boundary for River Rch & Prof#=Stream0229,Reach-1,3
Up Type=0
Dn Type=3
Dn Slope=0.005
Boundary for River Rch & Prof#=Stream0229,Reach-1,4
Up Type=0
Dn Type=3
Dn Slope=0.005
Boundary for River Rch & Prof#=Stream0229,Reach-1,5
Up Type=0
Dn Type=3
Dn Slope=0.005
Boundary for River Rch & Prof#=Stream0229,Reach-1,6
Up Type=0
Dn Type=3
Dn Slope=0.005
Boundary for River Rch & Prof#=Stream0229,Reach-1,7
Up Type=0
Dn Type=3
Dn Slope=0.005

--- Stream0229.g01 (geometry) ---

Geom Title=Existing Conditions

River Reach=Stream0229,Reach-1
Reach XY= 30
      1792075.00     13879925.00      1792113.85     13880024.53
      1792680.93     13879777.24      1793069.07     13879772.76
      1793526.47     13879328.53      1793875.10     13879417.67
      1794018.95     13879326.59      1795468.81     13880717.19
      1796219.14     13880827.06      1796581.34     13881033.02
      1796769.48     13881272.57      1797435.63     13882685.00
      1797758.37     13882908.29      1797868.50     13883167.27
      1798808.35     13883658.32      1799519.53     13884872.55
      1799554.51     13885055.21      1800030.85     13885372.94
      1800425.00     13885325.00      1800625.00     13885725.00
      1801314.46     13885726.08      1801719.38     13885930.62
      1801971.24     13886326.56      1802241.64     13887141.68
      1802471.59     13887367.18      1802568.95     13887326.67
      1802985.44     13887523.94      1803681.52     13887582.67
      1803724.68     13888009.95      1803625.00     13888075.00

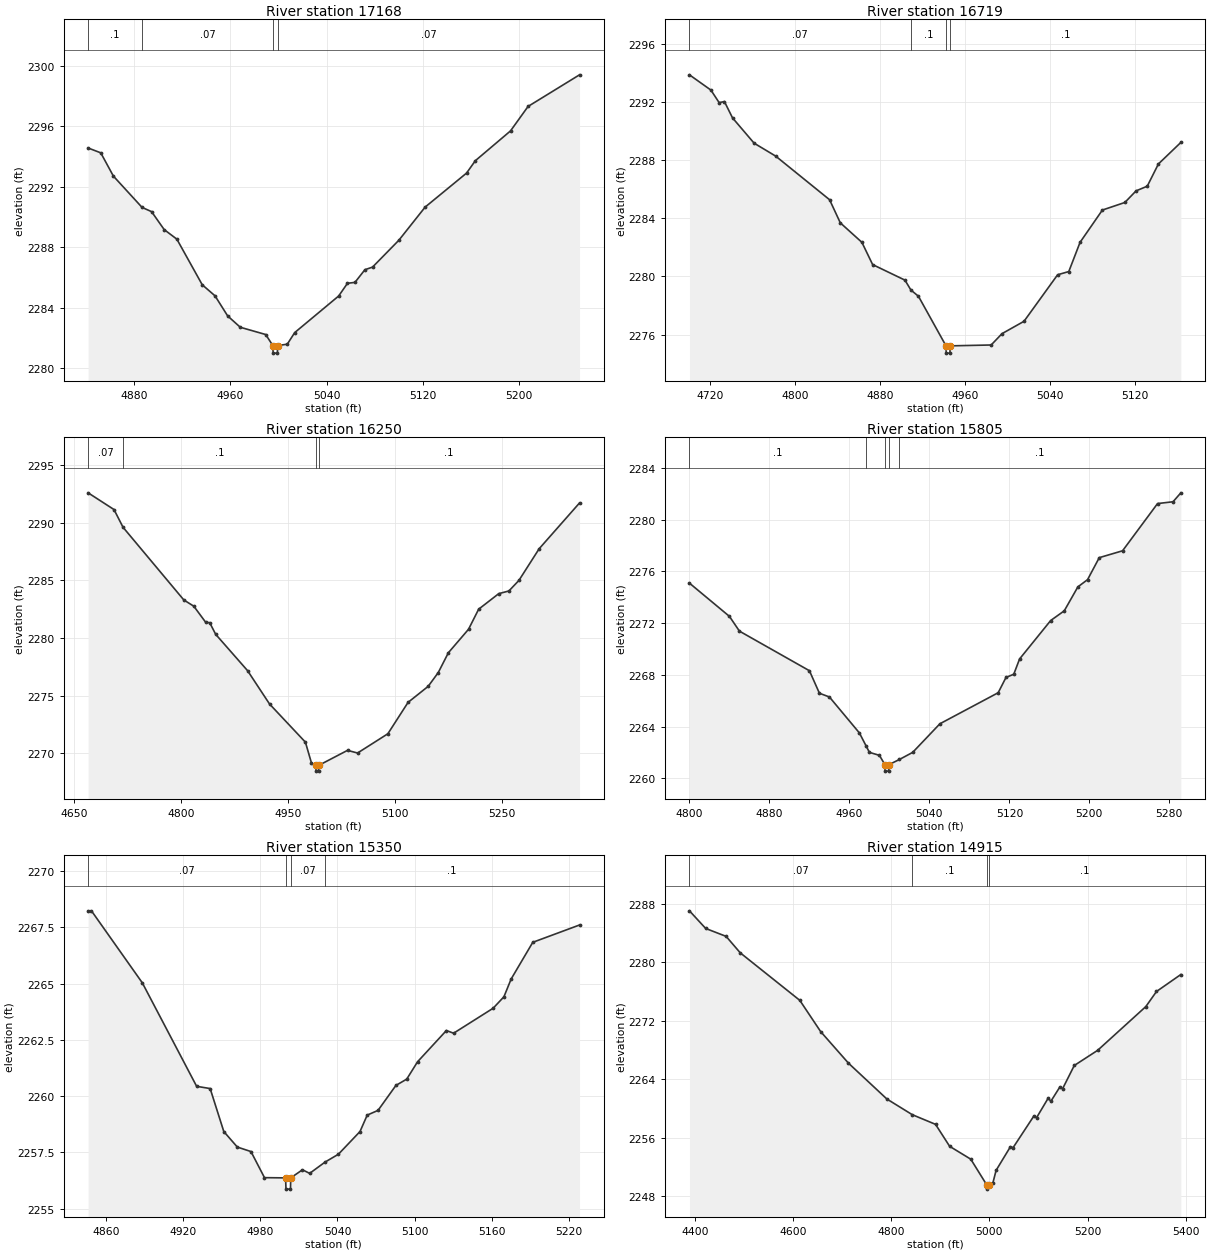
Type RM Length L Ch R = 1,17168,449,449,449
BEGIN DESCRIPTION:
Stream0229 36.0
END DESCRIPTION:
XS GIS Cut Line= 3
      1792324.99     13880074.96      1792275.00     13879925.00
      1792124.98     13879724.98
#Sta/Elev= 30
  4841.9 2294.56  4852.4 2294.24  4862.9 2292.70  4886.7 2290.63  4894.6 2290.35
  4905.1 2289.16  4915.6 2288.53  4936.7 2285.51  4947.3 2284.78  4957.8 2283.45
  4968.3 2282.70  4989.4 2282.22  4995.3 2281.49  4995.6 2280.99  4999.1 2280.99
  4999.3 2281.49  5007.3 2281.58  5013.5 2282.35  5050.0 2284.77  5057.3 2285.61
  5063.5 2285.67  5071.8 2286.51  5078.1 2286.68  5100.0 2288.46  5121.8 2290.65
  5156.2 2292.90  5163.5 2293.72  5192.7 2295.69  5207.3 2297.31  5250.0 2299.40
#Mann=4,-1,0
  4841.9     0.1       0  4886.7    0.07       0  4995.3    0.05       0
  4999.3    0.07       0
Bank Sta=4995.3,4999.3
Exp/Cntr=0.3,0.1

Type RM Length L Ch R = 1,16719,469,469,469
BEGIN DESCRIPTION:
Stream0229 35.0
END DESCRIPTION:
XS GIS Cut Line= 3
      1792625.00     13880074.97      1792675.00     13879775.00
      1792625.01     13879625.02
#Sta/Elev= 30
  4700.9 2293.86  4721.1 2292.81  4728.8 2291.95  4733.8 2292.02  4741.4 2290.90
  4761.7 2289.16  4782.0 2288.27  4832.7 2285.27  4842.8 2283.68  4863.1 2282.34
  4873.2 2280.81  4903.6 2279.74  4909.2 2279.06  4916.3 2278.63  4942.2 2275.22
  4942.4 2274.72  4945.9 2274.72  4946.2 2275.22  4984.7 2275.28  4994.9 2276.06
  5015.6 2276.91  5047.2 2280.11  5057.7 2280.33  5068.3 2282.34  5089.3 2284.56
  5110.4 2285.08  5121.0 2285.88  5131.5 2286.20  5142.0 2287.73  5163.1 2289.21
#Mann=4,-1,0
  4700.9    0.07       0  4909.2     0.1       0  4942.2    0.05       0
  4946.2     0.1       0
Bank Sta=4942.2,4946.2
Exp/Cntr=0.3,0.1

Type RM Length L Ch R = 1,16250,445,445,445
BEGIN DESCRIPTION:
Stream0229 34.0
END DESCRIPTION:
XS GIS Cut Line= 3
      1793275.01     13880025.01      1793125.00     13879725.00
      1792874.98     13879474.98
#Sta/Elev= 30
  4669.2 2292.59  4705.5 2291.14  4718.2 2289.60  4803.4 2283.30  4817.4 2282.76
  4834.1 2281.36  4839.7 2281.33  4848.1 2280.32  4892.8 2277.17  4923.6 2274.28
  4973.9 2270.97  4982.3 2269.18  4988.6 2268.96  4988.9 2268.46  4992.4 2268.46
  4992.6 2268.96  5032.9 2270.26  5047.0 2270.03  5089.5 2271.70  5117.8 2274.42
  5146.0 2275.81  5160.2 2277.01  5174.3 2278.72  5202.6 2280.76  5216.8 2282.50
  5245.0 2283.85  5259.2 2284.08  5273.3 2285.00  5301.6 2287.74  5358.2 2291.71
#Mann=4,-1,0
  4669.2    0.07       0  4718.2     0.1       0  4988.6    0.05       0
  4992.6     0.1       0
Bank Sta=4988.6,4992.6
Exp/Cntr=0.3,0.1

Type RM Length L Ch R = 1,15805,455,455,455
BEGIN DESCRIPTION:
Stream0229 33.0
END DESCRIPTION:
XS GIS Cut Line= 3
      1793425.00     13879624.97      1793425.00     13879425.00
      1793175.02     13879275.01
#Sta/Elev= 30
  4800.0 2275.09  4840.0 2272.52  4850.0 2271.38  4920.0 2268.32  4930.0 2266.58
  4940.0 2266.29  4970.0 2263.51  4976.8 2262.49  4980.0 2262.01  4990.0 2261.78
  4995.5 2261.06  4995.7 2260.56  4999.2 2260.56  4999.5 2261.06  5010.0 2261.46
  5023.3 2262.01  5050.5 2264.22  5108.8 2266.62  5116.6 2267.80  5124.4 2268.05
  5130.2 2269.23  5161.3 2272.20  5174.9 2272.95  5188.5 2274.80  5198.2 2275.36
  5209.9 2277.06  5233.2 2277.59  5268.2 2281.24  5283.7 2281.38  5291.5 2282.07
#Mann=5,-1,0
  4800.0     0.1       0  4976.8    0.07       0  4995.5    0.05       0
  4999.5    0.07       0  5010.0     0.1       0
Bank Sta=4995.5,4999.5
Exp/Cntr=0.3,0.1

Type RM Length L Ch R = 1,15350,435,435,435
BEGIN DESCRIPTION:
Stream0229 32.0
END DESCRIPTION:
XS GIS Cut Line= 3
      1793775.01     13879524.97      1793825.00     13879375.00
      1793725.00     13879174.99
#Sta/Elev= 30
  4846.3 2268.24  4848.9 2268.24  4888.4 2265.04  4930.6 2260.44  4941.1 2260.34
  4951.7 2258.43  4962.2 2257.74  4972.8 2257.54  4983.3 2256.38  4999.7 2256.37
  5000.0 2255.87  5003.5 2255.87  5003.7 2256.37  5012.8 2256.73  5018.4 2256.57
  5030.3 2257.07  5040.7 2257.42  5057.5 2258.43  5063.1 2259.16  5071.5 2259.37
  5085.4 2260.48  5093.8 2260.76  5102.2 2261.53  5124.6 2262.92  5130.2 2262.80
  5160.9 2263.91  5169.3 2264.42  5174.9 2265.21  5191.7 2266.84  5228.0 2267.61
#Mann=4,-1,0
  4846.3    0.07       0  4999.7    0.05       0  5003.7    0.07       0
  5030.3     0.1       0
Bank Sta=4999.7,5003.7
Exp/Cntr=0.3,0.1

Type RM Length L Ch R = 1,14915,467,467,467
BEGIN DESCRIPTION:
Stream0229 31.0
END DESCRIPTION:
XS GIS Cut Line= 3
      1793786.26     13879902.19      1794175.00     13879425.00
      1794323.49     13879069.24
#Sta/Elev= 30
  4389.1 2287.02  4422.2 2284.61  4463.8 2283.53  4492.6 2281.28  4613.9 2274.79
  4656.3 2270.53  4713.0 2266.21  4791.3 2261.31  4843.0 2259.17  4890.4 2257.85
  4919.1 2254.85  4962.2 2253.09  4995.4 2249.50  4995.7 2249.00  4999.4 2249.50
  5007.3 2249.87  5013.8 2251.57  5043.0 2254.80  5048.4 2254.67  5090.7 2258.99
  5096.1 2258.75  5119.9 2261.43  5125.3 2261.00  5143.7 2262.96  5149.1 2262.70
  5173.0 2265.89  5220.6 2267.96  5318.8 2273.94  5340.5 2276.00  5390.1 2278.32
#Mann=4,-1,0
  4389.1    0.07       0  4843.0     0.1       0  4995.4    0.05       0
  4999.4     0.1       0
Bank Sta=4995.4,4999.4
Exp/Cntr=0.3,0.1

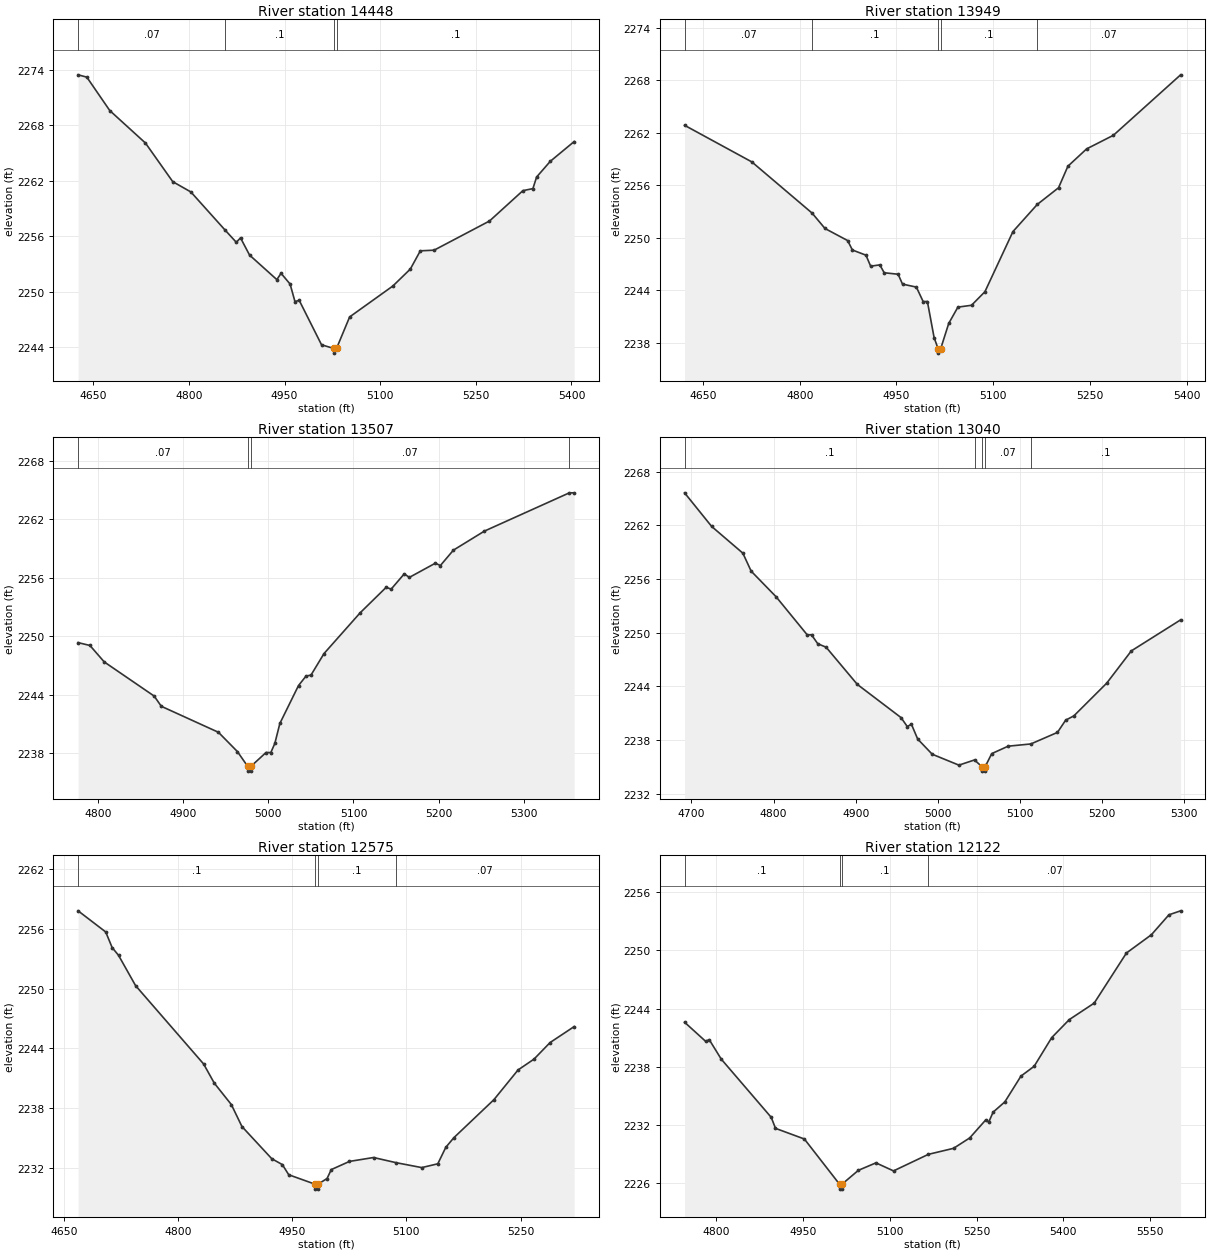
Type RM Length L Ch R = 1,14448,499,499,499
BEGIN DESCRIPTION:
Stream0229 30.0
END DESCRIPTION:
XS GIS Cut Line= 3
      1794197.45     13880017.00      1794475.00     13879775.00
      1794680.03     13879419.99
#Sta/Elev= 30
  4626.0 2273.44  4639.7 2273.19  4675.7 2269.58  4731.7 2266.07  4774.5 2261.90
  4802.9 2260.79  4856.6 2256.67  4874.2 2255.35  4880.8 2255.83  4895.0 2253.97
  4937.8 2251.32  4944.4 2252.00  4958.6 2250.84  4966.2 2248.95  4972.9 2249.08
  5007.9 2244.28  5027.4 2243.88  5027.7 2243.38  5031.4 2243.88  5052.0 2247.29
  5119.8 2250.63  5147.2 2252.46  5162.9 2254.43  5184.5 2254.50  5271.4 2257.65
  5323.8 2260.93  5339.5 2261.15  5345.3 2262.40  5366.8 2264.10  5404.2 2266.23
#Mann=4,-1,0
  4626.0    0.07       0  4856.6     0.1       0  5027.4    0.05       0
  5031.4     0.1       0
Bank Sta=5027.4,5031.4
Exp/Cntr=0.3,0.1

Type RM Length L Ch R = 1,13949,442,442,442
BEGIN DESCRIPTION:
Stream0229 29.0
END DESCRIPTION:
XS GIS Cut Line= 3
      1794550.92     13880378.60      1794825.00     13880125.00
      1795138.58     13879883.35
#Sta/Elev= 30
  4621.4 2262.87  4725.8 2258.68  4819.2 2252.83  4839.2 2251.07  4874.3 2249.69
  4881.7 2248.61  4902.7 2248.02  4910.0 2246.76  4924.2 2246.91  4931.0 2246.01
  4952.6 2245.84  4959.4 2244.71  4980.9 2244.37  4991.4 2242.72  4998.0 2242.72
  5008.4 2238.60  5014.6 2237.32  5014.8 2236.82  5018.6 2237.32  5031.1 2240.22
  5045.3 2242.08  5066.4 2242.29  5087.2 2243.84  5130.7 2250.72  5168.4 2253.82
  5201.4 2255.73  5215.9 2258.19  5244.9 2260.17  5286.5 2261.73  5390.7 2268.64
#Mann=5,-1,0
  4621.4    0.07       0  4819.2     0.1       0  5014.6    0.05       0
  5018.6     0.1       0  5168.4    0.07       0
Bank Sta=5014.6,5018.6
Exp/Cntr=0.3,0.1

Type RM Length L Ch R = 1,13507,467,467,467
BEGIN DESCRIPTION:
Stream0229 28.0
END DESCRIPTION:
XS GIS Cut Line= 3
      1794975.03     13880474.98      1795175.00     13880375.00
      1795479.46     13880184.15
#Sta/Elev= 30
  4776.4 2249.35  4790.3 2249.06  4807.1 2247.37  4865.8 2243.86  4874.2 2242.81
  4941.3 2240.14  4963.6 2238.16  4975.6 2236.65  4975.9 2236.15  4979.4 2236.15
  4979.6 2236.65  4997.2 2238.06  5002.9 2238.06  5007.6 2239.00  5013.5 2241.05
  5035.4 2244.94  5044.2 2245.91  5050.1 2246.02  5065.4 2248.23  5107.8 2252.41
  5138.4 2255.03  5144.3 2254.85  5159.7 2256.42  5165.6 2256.05  5196.2 2257.51
  5202.1 2257.27  5217.4 2258.85  5253.9 2260.81  5353.7 2264.74  5359.3 2264.74
#Mann=4,-1,0
  4776.4    0.07       0  4975.6    0.05       0  4979.6    0.07       0
  5353.7     0.1       0
Bank Sta=4975.6,4979.6
Exp/Cntr=0.3,0.1

Type RM Length L Ch R = 1,13040,465,465,465
BEGIN DESCRIPTION:
Stream0229 27.0
END DESCRIPTION:
XS GIS Cut Line= 3
      1795425.00     13881025.01      1795475.00     13880725.00
      1795475.00     13880425.04
#Sta/Elev= 30
  4691.6 2265.64  4724.6 2261.88  4762.6 2258.89  4772.7 2256.88  4803.1 2254.01
  4841.1 2249.74  4846.2 2249.76  4853.8 2248.76  4864.0 2248.37  4902.0 2244.21
  4955.2 2240.50  4962.8 2239.50  4967.9 2239.75  4975.5 2238.10  4993.2 2236.40
  5025.7 2235.18  5044.7 2235.76  5053.7 2235.01  5054.0 2234.51  5057.5 2234.51
  5057.7 2235.01  5065.7 2236.47  5085.7 2237.30  5113.3 2237.55  5145.7 2238.84
  5155.7 2240.21  5165.7 2240.69  5205.7 2244.35  5235.7 2247.96  5295.7 2251.43
#Mann=5,-1,0
  4691.6     0.1       0  5044.7    0.07       0  5053.7    0.05       0
  5057.7    0.07       0  5113.3     0.1       0
Bank Sta=5053.7,5057.7
Exp/Cntr=0.3,0.1

Type RM Length L Ch R = 1,12575,453,453,453
BEGIN DESCRIPTION:
Stream0229 26.0
END DESCRIPTION:
XS GIS Cut Line= 3
      1795775.00     13881075.01      1795925.00     13880775.00
      1796024.98     13880475.05
#Sta/Elev= 30
  4668.7 2257.79  4705.0 2255.67  4713.4 2254.11  4721.8 2253.33  4744.2 2250.29
  4833.6 2242.43  4847.6 2240.51  4870.0 2238.36  4883.9 2236.16  4923.1 2232.93
  4937.0 2232.34  4945.4 2231.32  4979.8 2230.38  4980.0 2229.88  4983.5 2229.88
  4983.8 2230.38  4995.7 2230.94  5001.3 2231.84  5025.2 2232.66  5056.8 2233.05
  5086.6 2232.53  5120.1 2232.04  5141.2 2232.42  5151.7 2234.07  5162.2 2235.03
  5214.9 2238.85  5246.6 2241.83  5267.6 2242.92  5288.7 2244.58  5320.3 2246.18
#Mann=4,-1,0
  4668.7     0.1       0  4979.8    0.05       0  4983.8     0.1       0
  5086.6    0.07       0
Bank Sta=4979.8,4983.8
Exp/Cntr=0.3,0.1

Type RM Length L Ch R = 1,12122,467,467,467
BEGIN DESCRIPTION:
Stream0229 25.0
END DESCRIPTION:
XS GIS Cut Line= 3
      1796125.02     13881074.98      1796325.00     13880925.00
      1796225.01     13880325.04
#Sta/Elev= 30
  4744.8 2242.59  4781.2 2240.62  4787.5 2240.79  4808.3 2238.78  4894.8 2232.77
  4902.1 2231.64  4952.1 2230.54  5013.0 2225.87  5013.3 2225.37  5016.8 2225.37
  5017.0 2225.87  5045.5 2227.31  5075.9 2228.08  5106.3 2227.25  5166.7 2228.96
  5210.2 2229.58  5238.1 2230.65  5266.0 2232.52  5271.0 2232.28  5278.6 2233.31
  5298.9 2234.37  5326.8 2237.03  5349.6 2238.04  5380.0 2241.00  5410.4 2242.86
  5453.5 2244.56  5509.3 2249.73  5552.4 2251.61  5582.8 2253.67  5603.0 2254.08
#Mann=4,-1,0
  4744.8     0.1       0  5013.0    0.05       0  5017.0     0.1       0
  5166.7    0.07       0
Bank Sta=5013,5017
Exp/Cntr=0.3,0.1

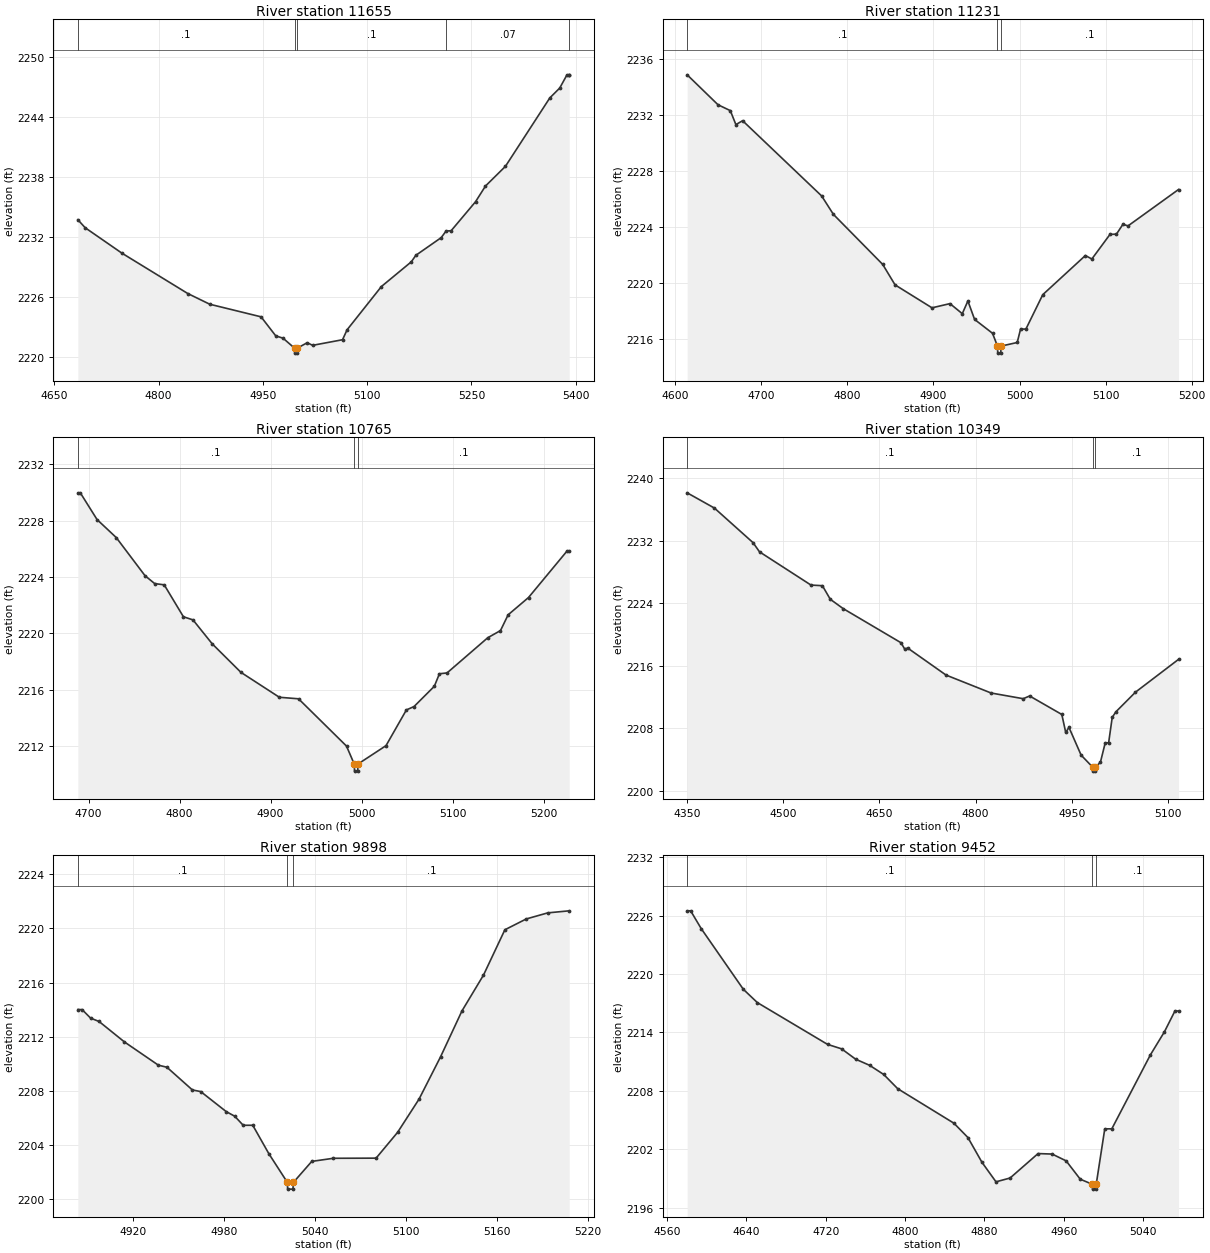
Type RM Length L Ch R = 1,11655,424,424,424
BEGIN DESCRIPTION:
Stream0229 24.0
END DESCRIPTION:
XS GIS Cut Line= 3
      1796374.99     13881275.00      1796675.00     13881175.00
      1796974.96     13880925.03
#Sta/Elev= 30
  4684.0 2233.75  4694.5 2232.95  4747.3 2230.41  4842.1 2226.37  4873.7 2225.30
  4947.5 2224.04  4968.6 2222.14  4979.2 2221.90  4995.6 2220.91  4995.9 2220.41
  4999.4 2220.41  4999.6 2220.91  5013.9 2221.45  5021.7 2221.19  5064.7 2221.75
  5071.2 2222.74  5120.6 2227.07  5163.6 2229.54  5170.1 2230.19  5206.6 2231.96
  5213.6 2232.62  5220.9 2232.65  5256.0 2235.55  5270.3 2237.12  5299.0 2239.09
  5362.8 2245.93  5377.1 2246.92  5387.5 2248.24  5390.3 2248.24  5390.7 2248.24
#Mann=5,-1,0
  4684.0     0.1       0  4995.6    0.05       0  4999.6     0.1       0
  5213.6    0.07       0  5390.3     0.1       0
Bank Sta=4995.6,4999.6
Exp/Cntr=0.3,0.1

Type RM Length L Ch R = 1,11231,466,466,466
BEGIN DESCRIPTION:
Stream0229 23.0
END DESCRIPTION:
XS GIS Cut Line= 3
      1796574.99     13881775.01      1796875.00     13881525.00
      1796975.00     13881375.00
#Sta/Elev= 30
  4613.9 2234.86  4649.7 2232.72  4664.0 2232.30  4670.5 2231.30  4678.3 2231.58
  4770.1 2226.20  4783.8 2224.88  4841.1 2221.30  4855.4 2219.84  4898.3 2218.20
  4919.2 2218.50  4933.5 2217.78  4940.0 2218.69  4947.8 2217.37  4968.6 2216.38
  4974.4 2215.46  4974.7 2214.96  4978.2 2214.96  4978.4 2215.46  4997.3 2215.72
  5001.2 2216.68  5007.4 2216.68  5027.0 2219.14  5076.5 2221.94  5084.0 2221.69
  5105.1 2223.45  5112.6 2223.47  5120.1 2224.17  5126.1 2224.06  5184.7 2226.66
#Mann=3,-1,0
  4613.9     0.1       0  4974.4    0.05       0  4978.4     0.1       0
Bank Sta=4974.4,4978.4
Exp/Cntr=0.3,0.1

Type RM Length L Ch R = 1,10765,416,416,416
BEGIN DESCRIPTION:
Stream0229 22.0
END DESCRIPTION:
XS GIS Cut Line= 3
      1796774.97     13882025.01      1797075.00     13881925.00
      1797275.03     13881824.99
#Sta/Elev= 30
  4688.3 2229.98  4691.0 2229.98  4709.4 2228.08  4730.5 2226.80  4762.1 2224.09
  4772.7 2223.53  4783.2 2223.44  4804.3 2221.17  4814.8 2220.95  4835.9 2219.25
  4867.5 2217.22  4909.7 2215.45  4930.8 2215.34  4983.5 2211.98  4992.0 2210.70
  4992.3 2210.20  4995.8 2210.20  4996.0 2210.70  5026.9 2212.01  5049.3 2214.55
  5057.7 2214.79  5080.0 2216.23  5085.6 2217.12  5094.0 2217.18  5138.7 2219.68
  5152.7 2220.19  5161.1 2221.31  5183.5 2222.54  5225.4 2225.81  5228.2 2225.81
#Mann=3,-1,0
  4688.3     0.1       0  4992.0    0.05       0  4996.0     0.1       0
Bank Sta=4992,4996
Exp/Cntr=0.3,0.1

Type RM Length L Ch R = 1,10349,451,451,451
BEGIN DESCRIPTION:
Stream0229 21.0
END DESCRIPTION:
XS GIS Cut Line= 3
      1796622.54     13882223.04      1797275.00     13882275.00
      1797374.98     13882225.01
#Sta/Elev= 30
  4350.3 2238.15  4392.9 2236.19  4453.1 2231.76  4463.1 2230.59  4543.4 2226.33
  4561.2 2226.25  4573.5 2224.51  4593.5 2223.32  4683.8 2218.94  4689.4 2218.15
  4694.4 2218.25  4754.0 2214.80  4824.3 2212.50  4874.4 2211.77  4884.4 2212.12
  4934.6 2209.75  4940.7 2207.44  4945.7 2208.10  4964.7 2204.54  4982.8 2202.99
  4983.0 2202.49  4986.5 2202.49  4986.8 2202.99  4994.8 2203.63  5002.3 2206.12
  5007.6 2206.12  5013.2 2209.37  5018.8 2210.08  5049.5 2212.61  5116.6 2216.81
#Mann=3,-1,0
  4350.3     0.1       0  4982.8    0.05       0  4986.8     0.1       0
Bank Sta=4982.8,4986.8
Exp/Cntr=0.3,0.1

Type RM Length L Ch R = 1,9898,446,446,446
BEGIN DESCRIPTION:
Stream0229 20.0
END DESCRIPTION:
XS GIS Cut Line= 3
      1797325.01     13882724.99      1797425.00     13882675.00
      1797574.98     13882525.02
#Sta/Elev= 30
  4883.6 2214.00  4886.4 2214.00  4892.0 2213.37  4897.6 2213.12  4914.3 2211.61
  4936.7 2209.89  4942.3 2209.74  4959.1 2208.06  4964.6 2207.94  4981.4 2206.46
  4987.0 2206.12  4992.6 2205.45  4998.9 2205.45  5009.5 2203.35  5021.7 2201.23
  5021.9 2200.73  5025.4 2200.73  5025.7 2201.23  5037.8 2202.78  5052.0 2203.01
  5080.2 2203.02  5094.4 2204.93  5108.5 2207.38  5122.7 2210.51  5136.8 2213.90
  5151.0 2216.55  5165.1 2219.90  5179.2 2220.70  5193.4 2221.15  5207.5 2221.30
#Mann=3,-1,0
  4883.6     0.1       0  5021.7    0.05       0  5025.7     0.1       0
Bank Sta=5021.7,5025.7
Exp/Cntr=0.3,0.1

Type RM Length L Ch R = 1,9452,446,446,446
BEGIN DESCRIPTION:
Stream0229 19.0
END DESCRIPTION:
XS GIS Cut Line= 3
      1797475.00     13883225.00      1797775.00     13882925.00
      1797825.02     13882874.98
#Sta/Elev= 30
  4580.5 2226.48  4584.0 2226.48  4594.6 2224.66  4637.1 2218.42  4651.2 2217.06
  4721.9 2212.77  4736.1 2212.31  4750.2 2211.25  4764.3 2210.62  4778.5 2209.68
  4792.6 2208.22  4849.2 2204.68  4863.3 2203.21  4877.5 2200.66  4891.6 2198.66
  4905.8 2199.05  4934.0 2201.56  4948.2 2201.51  4962.3 2200.81  4976.5 2198.93
  4988.6 2198.41  4988.9 2197.91  4992.4 2197.91  4992.6 2198.41  5001.2 2204.10
  5008.3 2204.10  5047.2 2211.70  5061.3 2214.06  5071.9 2216.20  5075.5 2216.20
#Mann=3,-1,0
  4580.5     0.1       0  4988.6    0.05       0  4992.6     0.1       0
Bank Sta=4988.6,4992.6
Exp/Cntr=0.3,0.1

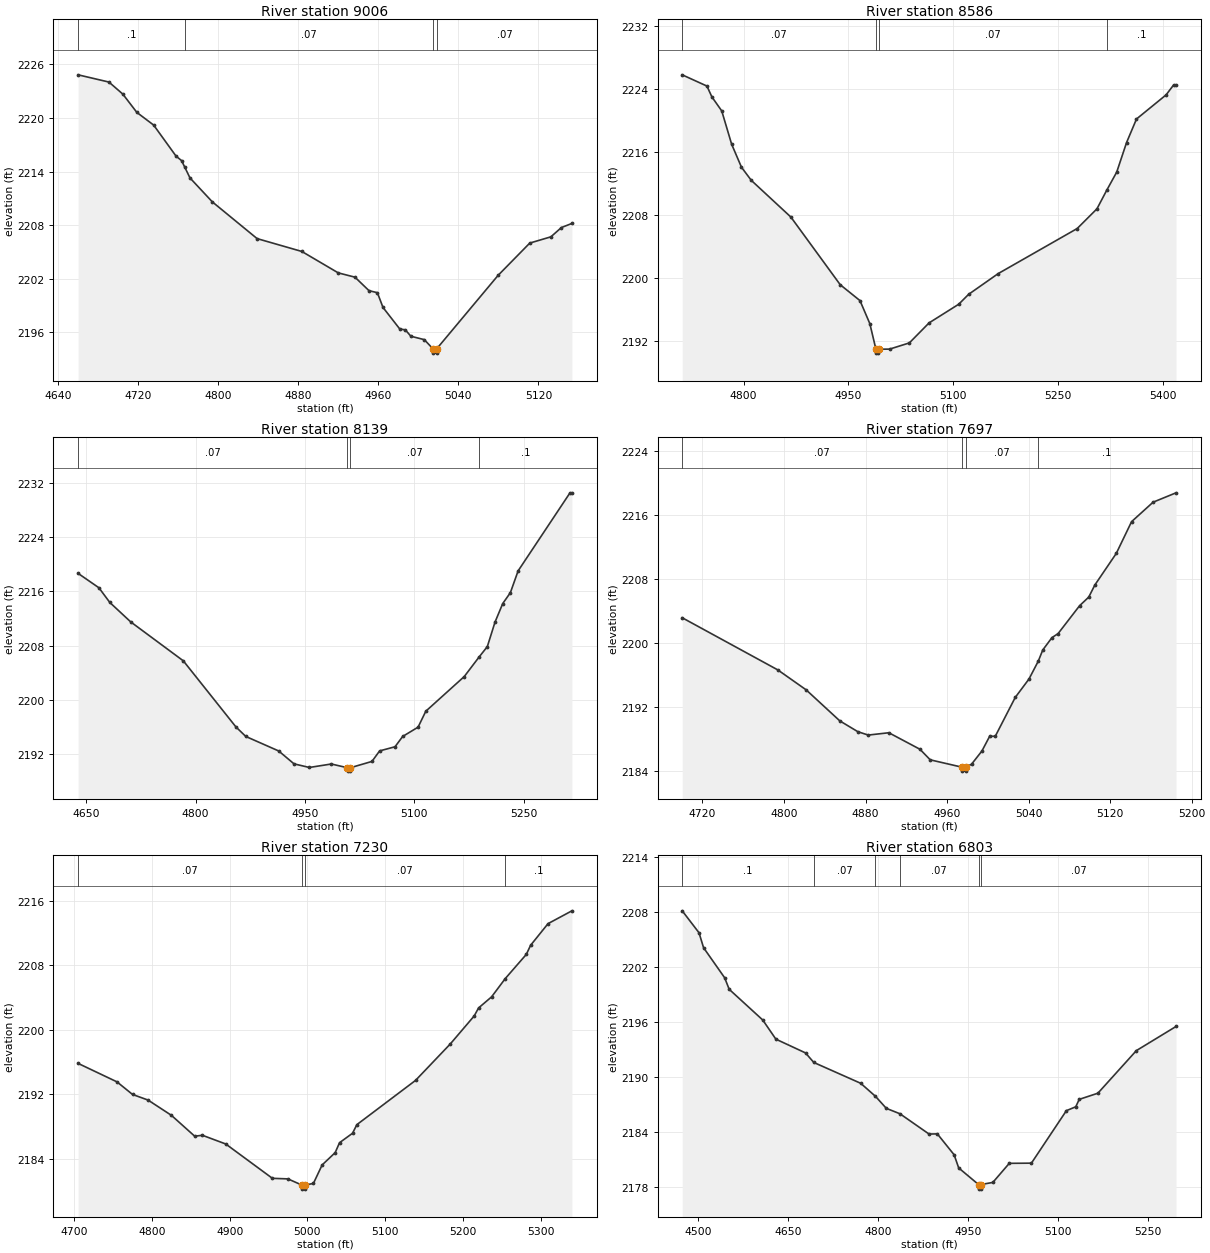
Type RM Length L Ch R = 1,9006,420,420,420
BEGIN DESCRIPTION:
Stream0229 18.0
END DESCRIPTION:
XS GIS Cut Line= 3
      1797874.99     13883525.02      1798025.00     13883225.00
      1798074.99     13883075.04
#Sta/Elev= 30
  4660.0 2224.84  4690.8 2224.03  4704.7 2222.68  4718.7 2220.63  4735.5 2219.21
  4757.9 2215.73  4763.4 2215.23  4766.7 2214.47  4771.8 2213.29  4794.2 2210.60
  4838.9 2206.49  4883.6 2205.05  4920.0 2202.65  4936.7 2202.17  4950.7 2200.66
  4959.1 2200.43  4964.7 2198.78  4981.5 2196.36  4987.0 2196.27  4992.6 2195.55
  5006.0 2195.17  5014.5 2194.16  5014.8 2193.66  5018.3 2193.66  5018.5 2194.16
  5079.8 2202.38  5111.4 2205.99  5132.5 2206.69  5143.0 2207.73  5153.5 2208.19
#Mann=4,-1,0
  4660.0     0.1       0  4766.7    0.07       0  5014.5    0.05       0
  5018.5    0.07       0
Bank Sta=5014.5,5018.5
Exp/Cntr=0.3,0.1

Type RM Length L Ch R = 1,8586,447,447,447
BEGIN DESCRIPTION:
Stream0229 17.0
END DESCRIPTION:
XS GIS Cut Line= 3
      1798174.97     13883625.03      1798375.00     13883425.00
      1798675.03     13883124.97
#Sta/Elev= 30
  4712.1 2225.83  4747.5 2224.40  4754.6 2223.02  4768.7 2221.24  4782.9 2217.00
  4797.0 2214.07  4811.1 2212.40  4867.7 2207.74  4938.4 2199.13  4966.7 2197.11
  4980.8 2194.18  4989.5 2190.93  4989.7 2190.43  4993.2 2190.43  4993.5 2190.93
  5009.1 2190.94  5037.4 2191.73  5065.7 2194.28  5108.1 2196.65  5122.3 2197.91
  5164.7 2200.55  5277.8 2206.28  5306.1 2208.79  5319.9 2211.12  5334.4 2213.46
  5348.5 2217.22  5362.7 2220.21  5405.1 2223.28  5415.7 2224.52  5419.3 2224.52
#Mann=4,-1,0
  4712.1    0.07       0  4989.5    0.05       0  4993.5    0.07       0
  5319.9     0.1       0
Bank Sta=4989.5,4993.5
Exp/Cntr=0.3,0.1

Type RM Length L Ch R = 1,8139,442,442,442
BEGIN DESCRIPTION:
Stream0229 16.0
END DESCRIPTION:
XS GIS Cut Line= 3
      1798425.04     13883774.97      1798725.00     13883575.00
      1799024.96     13883475.01
#Sta/Elev= 30
  4639.1 2218.65  4667.6 2216.53  4682.6 2214.36  4711.2 2211.50  4783.3 2205.76
  4855.4 2196.02  4868.9 2194.62  4914.0 2192.48  4935.0 2190.58  4956.0 2190.05
  4986.1 2190.56  5008.2 2190.01  5008.4 2189.51  5011.9 2189.51  5012.2 2190.01
  5041.8 2190.94  5052.3 2192.49  5073.4 2193.10  5083.9 2194.62  5105.0 2195.99
  5115.6 2198.34  5168.3 2203.45  5188.7 2206.34  5199.9 2207.86  5210.4 2211.46
  5221.0 2214.20  5231.5 2215.81  5242.1 2219.02  5313.2 2230.52  5315.8 2230.52
#Mann=4,-1,0
  4639.1    0.07       0  5008.2    0.05       0  5012.2    0.07       0
  5188.7     0.1       0
Bank Sta=5008.2,5012.2
Exp/Cntr=0.3,0.1

Type RM Length L Ch R = 1,7697,467,467,467
BEGIN DESCRIPTION:
Stream0229 15.0
END DESCRIPTION:
XS GIS Cut Line= 3
      1798675.02     13883975.00      1798975.00     13883925.00
      1799125.00     13883825.00
#Sta/Elev= 30
  4700.2 2203.14  4794.0 2196.63  4821.8 2194.14  4854.8 2190.27  4872.5 2188.92
  4882.7 2188.50  4902.9 2188.79  4933.4 2186.73  4943.5 2185.41  4974.4 2184.50
  4974.7 2184.00  4978.2 2184.00  4978.4 2184.50  4984.0 2184.86  4994.2 2186.51
  5001.8 2188.35  5007.3 2188.35  5026.9 2193.20  5040.4 2195.50  5049.5 2197.73
  5053.9 2199.12  5062.9 2200.66  5068.9 2201.16  5090.0 2204.64  5099.0 2205.72
  5105.0 2207.23  5126.0 2211.17  5141.0 2215.13  5162.1 2217.56  5184.6 2218.73
#Mann=4,-1,0
  4700.2    0.07       0  4974.4    0.05       0  4978.4    0.07       0
  5049.5     0.1       0
Bank Sta=4974.4,4978.4
Exp/Cntr=0.3,0.1

Type RM Length L Ch R = 1,7230,427,427,427
BEGIN DESCRIPTION:
Stream0229 14.0
END DESCRIPTION:
XS GIS Cut Line= 3
      1798874.96     13884325.00      1799175.00     13884325.00
      1799324.98     13884025.04
#Sta/Elev= 30
  4705.0 2195.83  4755.0 2193.54  4775.0 2191.98  4795.0 2191.28  4825.0 2189.39
  4855.0 2186.80  4865.0 2186.91  4895.0 2185.83  4955.0 2181.57  4975.0 2181.50
  4993.0 2180.73  4993.3 2180.23  4996.8 2180.23  4997.0 2180.73  5007.8 2180.94
  5019.0 2183.23  5035.8 2184.76  5041.4 2185.99  5058.1 2187.16  5063.7 2188.23
  5139.2 2193.72  5183.9 2198.24  5214.7 2201.72  5220.3 2202.71  5237.0 2204.08
  5254.7 2206.36  5281.7 2209.35  5287.3 2210.49  5309.7 2213.17  5340.4 2214.76
#Mann=4,-1,0
  4705.0    0.07       0  4993.0    0.05       0  4997.0    0.07       0
  5254.7     0.1       0
Bank Sta=4993,4997
Exp/Cntr=0.3,0.1

Type RM Length L Ch R = 1,6803,441,441,441
BEGIN DESCRIPTION:
Stream0229 13.0
END DESCRIPTION:
XS GIS Cut Line= 3
      1798975.02     13885024.98      1799375.00     13884675.00
      1799524.99     13884425.02
#Sta/Elev= 30
  4473.2 2208.13  4501.2 2205.74  4508.8 2204.11  4543.9 2200.84  4551.5 2199.58
  4607.5 2196.23  4629.3 2194.15  4678.7 2192.65  4692.5 2191.61  4770.7 2189.34
  4795.3 2187.92  4813.4 2186.61  4836.1 2186.02  4884.6 2183.81  4898.4 2183.83
  4926.4 2181.55  4934.0 2180.12  4967.1 2178.31  4967.3 2177.81  4970.8 2177.81
  4971.1 2178.31  4990.9 2178.54  5018.3 2180.62  5055.2 2180.64  5113.5 2186.36
  5129.1 2186.78  5134.9 2187.59  5166.0 2188.26  5230.1 2192.90  5296.2 2195.53
#Mann=6,-1,0
  4473.2     0.1       0  4692.5    0.07       0  4795.3     0.1       0
  4836.1    0.07       0  4967.1    0.05       0  4971.1    0.07       0
Bank Sta=4967.1,4971.1
Exp/Cntr=0.3,0.1

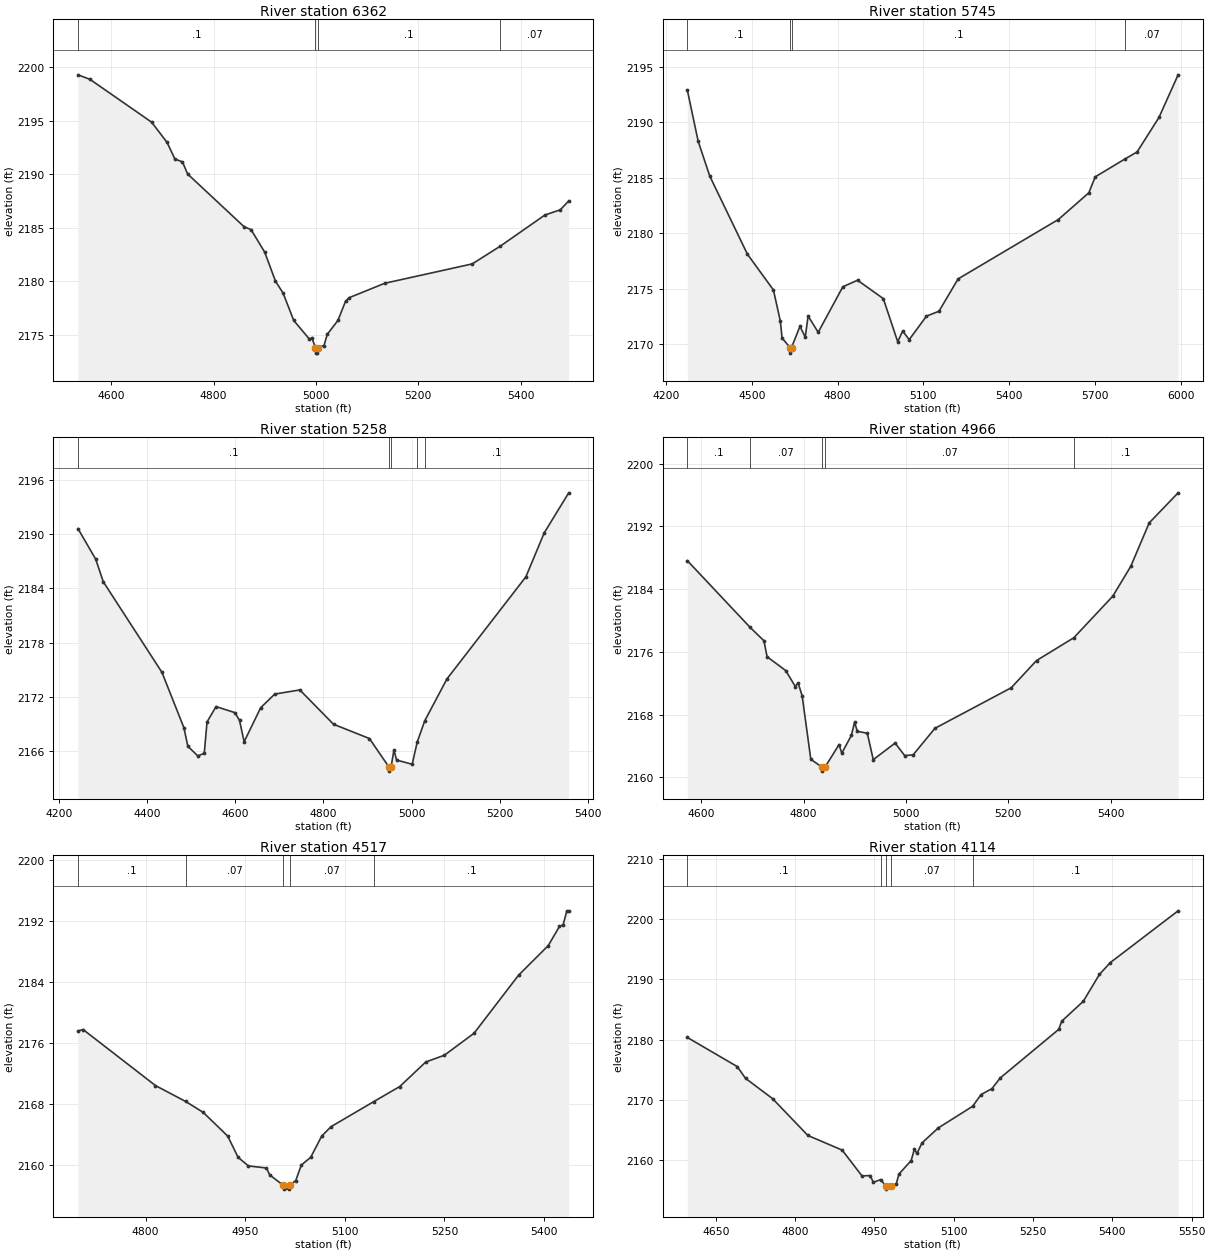
Type RM Length L Ch R = 1,6362,617,617,617
BEGIN DESCRIPTION:
Stream0229 12.1
END DESCRIPTION:
XS GIS Cut Line= 4
      1799111.76     13885158.46      1799448.31     13885125.56
      1799664.08     13884974.13      1799697.04     13884618.61
#Sta/Elev= 30
  4535.1 2199.28  4558.5 2198.86  4679.0 2194.86  4709.2 2192.97  4724.5 2191.42
  4739.3 2191.15  4749.4 2190.02  4859.9 2185.09  4873.3 2184.83  4900.0 2182.72
  4921.0 2180.02  4935.8 2178.91  4956.7 2176.35  4986.3 2174.66  4992.4 2174.69
  4999.1 2173.80  4999.4 2173.30  5002.9 2173.30  5003.1 2173.80  5015.8 2174.01
  5022.1 2175.05  5043.0 2176.35  5057.8 2178.13  5064.7 2178.47  5134.4 2179.82
  5305.5 2181.63  5359.7 2183.27  5447.3 2186.19  5477.4 2186.68  5493.9 2187.51
#Mann=4,-1,0
  4535.1     0.1       0  4999.1    0.05       0  5003.1     0.1       0
  5359.7    0.07       0
Bank Sta=4999.1,5003.1
Exp/Cntr=0.3,0.1

Type RM Length L Ch R = 1,5745,487,487,487
BEGIN DESCRIPTION:
Stream0229 12.0
END DESCRIPTION:
XS GIS Cut Line= 4
      1799941.45     13886092.47      1800039.11     13885448.48
      1800059.38     13885256.89      1799674.99     13884474.98
#Sta/Elev= 30
  4274.9 2192.93  4312.8 2188.30  4353.3 2185.16  4484.7 2178.12  4575.8 2174.88
  4599.9 2172.08  4606.1 2170.54  4634.0 2169.68  4634.3 2169.18  4639.0 2169.68
  4668.6 2171.60  4687.0 2170.62  4697.1 2172.53  4732.3 2171.06  4818.5 2175.17
  4869.8 2175.76  4959.9 2174.10  5010.2 2170.21  5027.5 2171.17  5050.4 2170.40
  5110.8 2172.52  5154.4 2172.96  5221.3 2175.88  5571.6 2181.24  5678.2 2183.65
  5700.5 2185.09  5804.9 2186.71  5846.9 2187.34  5923.3 2190.45  5990.2 2194.30
#Mann=4,-1,0
  4274.9     0.1       0  4634.0    0.05       0  4639.0     0.1       0
  5804.9    0.07       0
Bank Sta=4634,4639
Exp/Cntr=0.3,0.1

Type RM Length L Ch R = 1,5258,292,292,292
BEGIN DESCRIPTION:
Stream0229 11.1
END DESCRIPTION:
XS GIS Cut Line= 3
      1800211.96     13886073.33      1800431.37     13885397.27
      1800750.91     13885153.98
#Sta/Elev= 30
  4243.7 2190.64  4284.0 2187.24  4301.0 2184.75  4434.1 2174.69  4483.8 2168.55
  4492.8 2166.49  4515.3 2165.42  4530.0 2165.71  4536.3 2169.19  4556.7 2170.89
  4599.4 2170.22  4609.9 2169.36  4620.4 2166.99  4657.9 2170.77  4689.8 2172.28
  4746.6 2172.74  4823.0 2168.93  4904.3 2167.35  4948.0 2164.23  4948.5 2163.73
  4953.6 2164.23  4959.9 2166.08  4965.9 2164.96  5001.3 2164.49  5012.6 2166.94
  5029.7 2169.31  5080.2 2173.97  5259.0 2185.29  5300.7 2190.18  5356.1 2194.61
#Mann=5,-1,0
  4243.7     0.1       0  4948.0    0.05       0  4953.6     0.1       0
  5012.6    0.07       0  5029.7     0.1       0
Bank Sta=4948,4953.6
Exp/Cntr=0.3,0.1

Type RM Length L Ch R = 1,4966,449,449,449
BEGIN DESCRIPTION:
Stream0229 11.0
END DESCRIPTION:
XS GIS Cut Line= 3
      1800424.99     13886025.03      1800575.00     13885625.00
      1800924.97     13885225.03
#Sta/Elev= 30
  4572.9 2187.62  4695.7 2179.10  4722.5 2177.41  4728.7 2175.37  4765.2 2173.60
  4783.9 2171.56  4789.2 2172.05  4797.2 2170.39  4814.1 2162.29  4836.2 2161.28
  4836.7 2160.78  4841.8 2161.28  4869.3 2164.17  4874.6 2163.06  4893.3 2165.33
  4899.6 2167.02  4904.9 2165.86  4924.5 2165.61  4936.1 2162.24  4978.8 2164.36
  4997.5 2162.76  5013.9 2162.85  5056.6 2166.24  5205.6 2171.41  5255.0 2174.88
  5327.9 2177.79  5404.0 2183.09  5439.1 2186.89  5475.2 2192.44  5531.6 2196.27
#Mann=5,-1,0
  4572.9     0.1       0  4695.7    0.07       0  4836.2    0.05       0
  4841.8    0.07       0  5327.9     0.1       0
Bank Sta=4836.2,4841.8
Exp/Cntr=0.3,0.1

Type RM Length L Ch R = 1,4517,403,403,403
BEGIN DESCRIPTION:
Stream0229 10.0
END DESCRIPTION:
XS GIS Cut Line= 3
      1800774.98     13885975.03      1800925.00     13885725.00
      1801125.00     13885325.00
#Sta/Elev= 30
  4698.3 2177.62  4706.1 2177.79  4815.0 2170.45  4860.5 2168.36  4886.9 2166.93
  4923.8 2163.82  4939.3 2161.05  4954.9 2159.91  4982.1 2159.64  4987.0 2158.73
  5007.5 2157.37  5008.0 2156.87  5016.4 2156.87  5016.9 2157.37  5026.2 2158.00
  5034.6 2160.04  5048.6 2161.03  5065.3 2163.83  5079.3 2165.06  5143.7 2168.35
  5182.7 2170.32  5221.9 2173.54  5249.8 2174.42  5294.5 2177.30  5361.6 2184.92
  5406.3 2188.80  5423.1 2191.31  5428.7 2191.53  5434.3 2193.36  5437.1 2193.36
#Mann=5,-1,0
  4698.3     0.1       0  4860.5    0.07       0  5007.5    0.05       0
  5016.9    0.07       0  5143.7     0.1       0
Bank Sta=5007.5,5016.9
Exp/Cntr=0.3,0.1

Type RM Length L Ch R = 1,4114,474,474,474
BEGIN DESCRIPTION:
Stream0229 9.0
END DESCRIPTION:
XS GIS Cut Line= 3
      1801075.02     13886074.96      1801275.00     13885725.00
      1801178.32     13885208.75
#Sta/Elev= 30
  4596.1 2180.35  4690.4 2175.52  4706.2 2173.56  4757.3 2170.19  4824.2 2164.07
  4889.0 2161.64  4926.5 2157.35  4941.6 2157.42  4948.1 2156.30  4962.0 2156.75
  4971.3 2155.66  4971.8 2155.16  4980.9 2155.66  4991.3 2156.04  4996.3 2157.65
  5019.5 2159.91  5025.5 2161.77  5030.6 2161.10  5039.9 2162.82  5070.4 2165.30
  5135.8 2168.92  5151.8 2170.87  5172.1 2171.84  5188.3 2173.65  5298.6 2181.69
  5304.4 2183.06  5345.1 2186.36  5375.6 2190.82  5396.0 2192.77  5524.4 2201.38
#Mann=5,-1,0
  4596.1     0.1       0  4962.0    0.07       0  4971.3    0.05       0
  4980.9    0.07       0  5135.8     0.1       0
Bank Sta=4971.3,4980.9
Exp/Cntr=0.3,0.1