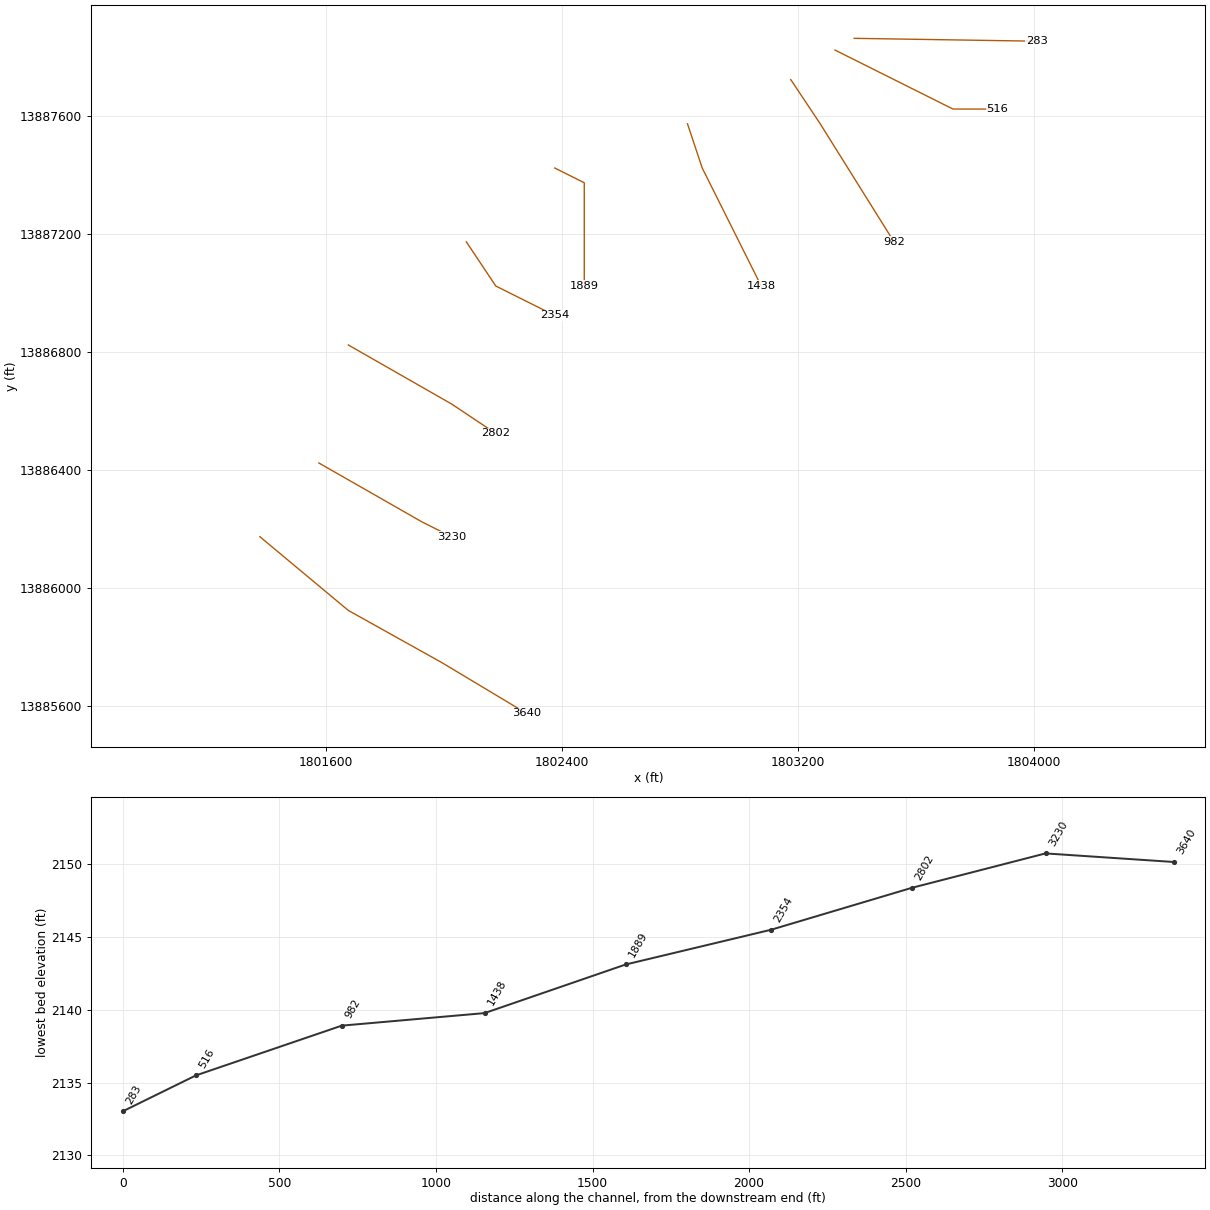
HEC-RAS study Stream0229.prj: Stream0229 Base Level Engineering

--- Stream0229.g01 (geometry) --- (continued)

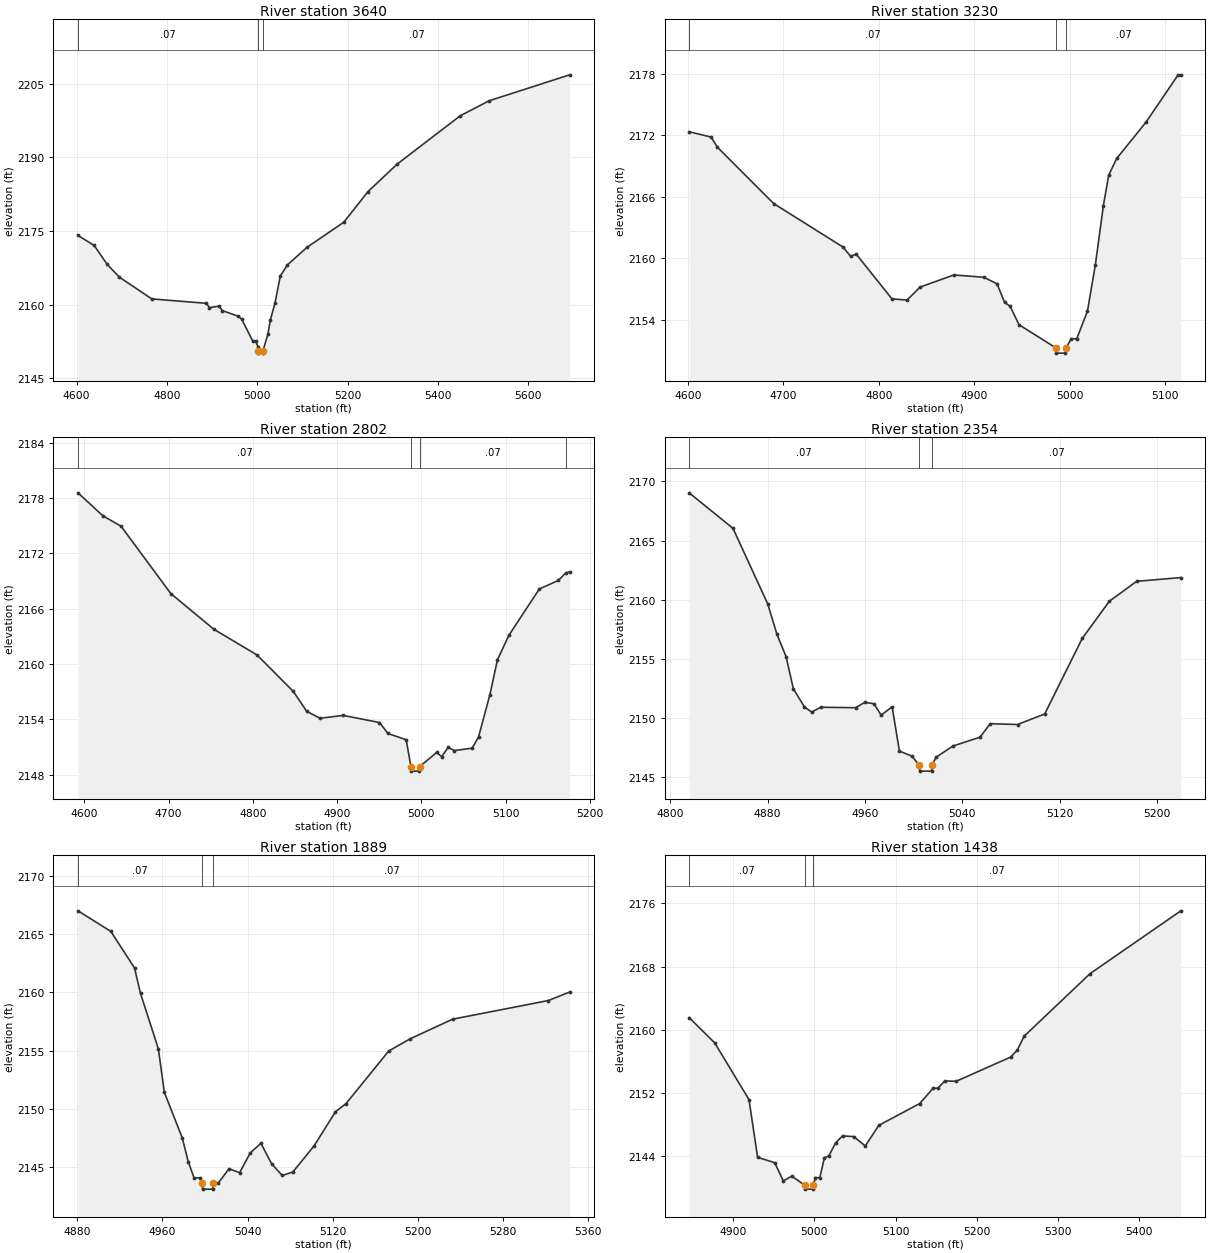
Type RM Length L Ch R = 1,3640,410,410,410
BEGIN DESCRIPTION:
Stream0229 8.0
END DESCRIPTION:
XS GIS Cut Line= 4
      1801375.02     13886174.99      1801675.00     13885925.00
      1801990.06     13885749.21      1802279.14     13885575.95
#Sta/Elev= 30
  4603.3 2174.09  4639.1 2172.07  4667.7 2168.23  4695.0 2165.60  4766.6 2161.19
  4887.7 2160.29  4894.2 2159.41  4915.7 2159.71  4922.8 2158.81  4958.0 2157.67
  4965.8 2157.04  4990.5 2152.53  4996.7 2152.53  5001.8 2151.45  5002.3 2150.66
  5002.8 2150.16  5012.2 2150.16  5012.7 2150.66  5023.5 2153.98  5029.2 2156.92
  5039.5 2160.42  5051.0 2165.83  5066.9 2168.11  5110.3 2171.69  5191.5 2176.78
  5245.2 2183.02  5310.3 2188.65  5449.0 2198.42  5513.2 2201.49  5691.6 2206.77
#Mann=3,-1,0
  4603.3    0.07       0  5002.3    0.05       0  5012.7    0.07       0
Bank Sta=5002.3,5012.7
Exp/Cntr=0.3,0.1

Type RM Length L Ch R = 1,3230,428,428,428
BEGIN DESCRIPTION:
Stream0229 7.0
END DESCRIPTION:
XS GIS Cut Line= 3
      1801575.03     13886424.98      1801925.00     13886225.00
      1802025.02     13886174.99
#Sta/Elev= 30
  4601.5 2172.34  4624.5 2171.82  4631.0 2170.84  4690.0 2165.34  4762.7 2161.09
  4770.6 2160.19  4776.4 2160.41  4813.8 2156.05  4829.7 2155.92  4843.3 2157.19
  4878.6 2158.37  4910.3 2158.15  4924.0 2157.50  4931.9 2155.69  4937.6 2155.32
  4947.0 2153.52  4985.7 2151.25  4986.2 2150.75  4995.6 2150.75  4996.1 2151.25
  5001.7 2152.15  5007.4 2152.15  5018.6 2154.84  5026.9 2159.36  5035.3 2165.14
  5040.9 2168.11  5049.3 2169.74  5080.0 2173.28  5113.6 2177.89  5116.4 2177.89
#Mann=3,-1,0
  4601.5    0.07       0  4985.7    0.05       0  4996.1    0.07       0
Bank Sta=4985.7,4996.1
Exp/Cntr=0.3,0.1

Type RM Length L Ch R = 1,2802,448,448,448
BEGIN DESCRIPTION:
Stream0229 6.0
END DESCRIPTION:
XS GIS Cut Line= 3
      1801675.02     13886824.99      1802025.00     13886625.00
      1802175.02     13886524.98
#Sta/Elev= 30
  4592.6 2178.55  4622.1 2176.06  4643.7 2174.93  4702.7 2167.63  4753.8 2163.76
  4804.9 2160.98  4848.1 2157.02  4864.0 2154.86  4879.8 2154.11  4907.2 2154.42
  4950.3 2153.65  4960.4 2152.46  4982.0 2151.78  4987.6 2148.88  4988.1 2148.38
  4997.6 2148.38  4998.1 2148.88  5018.2 2150.41  5024.2 2149.94  5031.7 2150.96
  5039.3 2150.61  5060.3 2150.87  5067.8 2152.07  5081.3 2156.66  5090.3 2160.46
  5103.9 2163.11  5139.9 2168.12  5162.5 2169.05  5171.2 2169.85  5176.0 2169.99
#Mann=4,-1,0
  4592.6    0.07       0  4987.6    0.05       0  4998.1    0.07       0
  5171.2     0.1       0
Bank Sta=4987.6,4998.1
Exp/Cntr=0.3,0.1

Type RM Length L Ch R = 1,2354,465,465,465
BEGIN DESCRIPTION:
Stream0229 5.0
END DESCRIPTION:
XS GIS Cut Line= 3
      1802075.03     13887174.96      1802175.00     13887025.00
      1802374.97     13886925.02
#Sta/Elev= 30
  4815.6 2169.03  4851.6 2166.03  4880.2 2159.63  4887.7 2157.08  4895.2 2155.19
  4901.2 2152.47  4910.2 2150.95  4916.2 2150.50  4923.7 2150.91  4952.3 2150.87
  4959.8 2151.32  4967.3 2151.21  4973.3 2150.24  4982.3 2150.95  4988.3 2147.20
  4998.6 2146.78  5004.5 2146.01  5005.0 2145.51  5014.7 2145.51  5015.2 2146.01
  5018.2 2146.67  5032.2 2147.63  5054.5 2148.38  5062.9 2149.52  5085.3 2149.45
  5107.6 2150.34  5138.4 2156.72  5160.7 2159.87  5183.1 2161.55  5219.4 2161.87
#Mann=3,-1,0
  4815.6    0.07       0  5004.5    0.05       0  5015.2    0.07       0
Bank Sta=5004.5,5015.2
Exp/Cntr=0.3,0.1

Type RM Length L Ch R = 1,1889,451,451,451
BEGIN DESCRIPTION:
Stream0229 4.0
END DESCRIPTION:
XS GIS Cut Line= 3
      1802374.97     13887425.01      1802475.00     13887375.00
      1802475.00     13887025.04
#Sta/Elev= 30
  4880.8 2166.98  4911.6 2165.22  4933.9 2162.08  4939.5 2159.90  4956.3 2155.14
  4961.9 2151.42  4978.7 2147.52  4984.3 2145.48  4989.8 2144.09  4995.1 2144.09
  4997.3 2143.62  4997.8 2143.12  5007.5 2143.12  5008.0 2143.62  5012.6 2143.65
  5022.6 2144.87  5032.6 2144.53  5042.6 2146.23  5052.6 2147.05  5062.6 2145.30
  5072.6 2144.29  5082.6 2144.59  5102.6 2146.84  5122.6 2149.75  5132.6 2150.46
  5172.6 2154.96  5192.6 2156.00  5232.6 2157.69  5322.6 2159.29  5342.6 2160.02
#Mann=3,-1,0
  4880.8    0.07       0  4997.3    0.05       0  5008.0    0.07       0
Bank Sta=4997.3,5008
Exp/Cntr=0.3,0.1

Type RM Length L Ch R = 1,1438,456,456,456
BEGIN DESCRIPTION:
Stream0229 3.0
END DESCRIPTION:
XS GIS Cut Line= 3
      1802825.01     13887574.96      1802875.00     13887425.00
      1803075.01     13887024.98
#Sta/Elev= 30
  4845.8 2161.53  4877.4 2158.31  4919.5 2151.13  4930.1 2143.82  4951.2 2143.13
  4961.7 2140.82  4972.2 2141.43  4987.9 2140.28  4988.4 2139.78  4998.2 2139.78
  4998.7 2140.28  5001.2 2141.24  5006.7 2141.24  5012.3 2143.74  5017.8 2144.00
  5026.2 2145.66  5034.6 2146.53  5048.6 2146.44  5062.6 2145.25  5079.3 2147.87
  5129.6 2150.63  5146.4 2152.60  5152.0 2152.56  5160.4 2153.50  5174.4 2153.45
  5241.5 2156.52  5249.8 2157.41  5258.2 2159.17  5339.3 2167.10  5451.1 2175.07
#Mann=3,-1,0
  4845.8    0.07       0  4987.9    0.05       0  4998.7    0.07       0
Bank Sta=4987.9,4998.7
Exp/Cntr=0.3,0.1

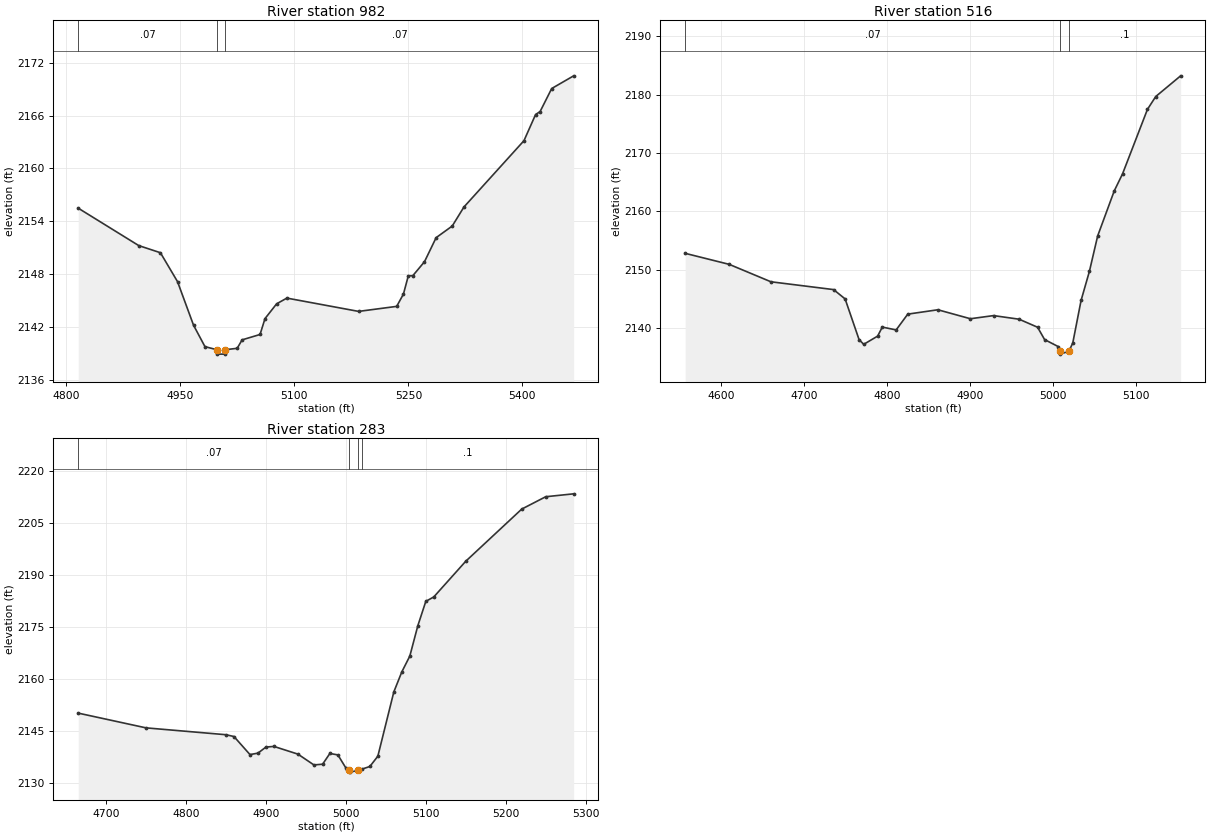
Type RM Length L Ch R = 1,982,466,466,466
BEGIN DESCRIPTION:
Stream0229 2.0
END DESCRIPTION:
XS GIS Cut Line= 3
      1803174.98     13887725.03      1803275.00     13887575.00
      1803525.00     13887175.01
#Sta/Elev= 30
  4815.5 2155.49  4895.2 2151.24  4923.7 2150.43  4946.2 2147.15  4967.3 2142.20
  4982.3 2139.77  4998.0 2139.42  4998.5 2138.92  5008.4 2138.92  5008.9 2139.42
  5024.7 2139.58  5031.2 2140.54  5054.8 2141.15  5061.3 2142.95  5076.6 2144.63
  5090.1 2145.28  5184.5 2143.77  5234.6 2144.34  5243.5 2145.74  5249.9 2147.81
  5255.8 2147.82  5271.2 2149.41  5286.5 2152.14  5307.7 2153.46  5323.1 2155.62
  5402.1 2163.15  5417.4 2166.12  5423.3 2166.45  5438.6 2169.07  5467.5 2170.51
#Mann=3,-1,0
  4815.5    0.07       0  4998.0    0.05       0  5008.9    0.07       0
Bank Sta=4998,5008.9
Exp/Cntr=0.3,0.1

Type RM Length L Ch R = 1,516,233,233,233
BEGIN DESCRIPTION:
Stream0229 1.0
END DESCRIPTION:
XS GIS Cut Line= 3
      1803325.03     13887824.99      1803725.00     13887625.00
      1803875.02     13887625.00
#Sta/Elev= 30
  4556.5 2152.79  4609.6 2150.90  4659.9 2147.91  4735.4 2146.57  4749.3 2144.97
  4766.1 2138.00  4771.7 2137.18  4788.5 2138.59  4794.1 2140.14  4810.8 2139.65
  4824.8 2142.36  4861.1 2143.11  4900.3 2141.57  4928.2 2142.11  4959.0 2141.49
  4981.3 2140.11  4989.7 2138.00  5006.2 2136.79  5008.2 2136.00  5008.7 2135.50
  5019.1 2136.00  5023.7 2137.42  5033.7 2144.71  5043.7 2149.68  5053.7 2155.78
  5073.7 2163.51  5083.7 2166.43  5113.7 2177.49  5123.7 2179.69  5153.7 2183.24
#Mann=3,-1,0
  4556.5    0.07       0  5008.2    0.05       0  5019.1     0.1       0
Bank Sta=5008.2,5019.1
Exp/Cntr=0.3,0.1

Type RM Length L Ch R = 1,283,0,0,0
BEGIN DESCRIPTION:
Stream0229 0.0
END DESCRIPTION:
XS GIS Cut Line= 2
      1803390.16     13887864.74      1804009.98     13887855.00
#Sta/Elev= 30
  4665.1 2150.08  4750.0 2145.82  4850.0 2143.84  4860.0 2143.32  4880.0 2138.11
  4890.0 2138.52  4900.0 2140.28  4910.0 2140.46  4940.0 2138.24  4960.0 2135.12
  4970.9 2135.33  4980.0 2138.43  4990.0 2138.01  5000.0 2134.24  5004.5 2133.54
  5005.0 2133.04  5015.4 2133.54  5020.3 2133.92  5030.0 2134.67  5040.0 2137.64
  5060.0 2156.21  5070.0 2161.99  5080.0 2166.55  5090.0 2175.30  5100.0 2182.35
  5110.0 2183.63  5150.0 2193.94  5220.0 2208.99  5250.0 2212.56  5285.0 2213.40
#Mann=4,-1,0
  4665.1    0.07       0  5004.5    0.05       0  5015.4    0.07       0
  5020.3     0.1       0
Bank Sta=5004.5,5015.4
Exp/Cntr=0.3,0.1

Chan Stop Cuts=-1