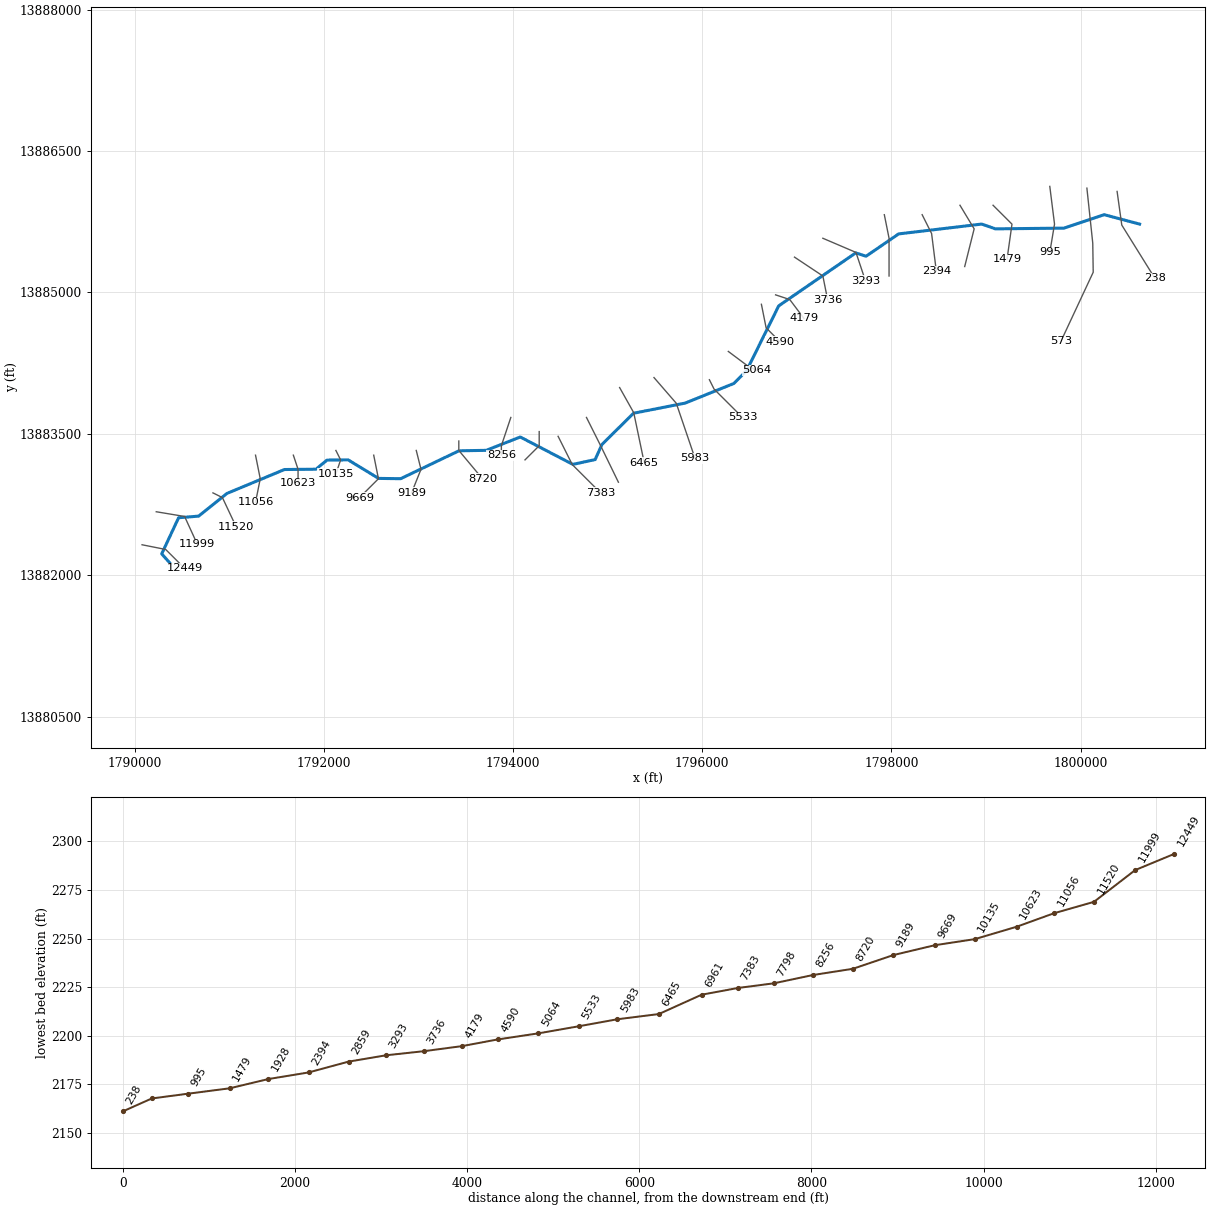
--- Stream0231.prj (project) ---

Proj Title=Stream0231 Base Level Engineering
Current Plan=p01
Default Exp/Contr=0.3,0.1
English Units
Geom File=g01
Flow File=f01
Plan File=p01
BEGIN DESCRIPTION:
Stream0231
END DESCRIPTION:

--- Stream0231.p01 (plan) ---

Plan Title=Multiple Run
Short Identifier=Multiple
Geom File=g01
Flow File=f01
Subcritical Flow
K Sum by GR= 0
Std Step Tol= 0.01
Critical Tol= 0.01
Num of Std Step Trials= 20
Max Error Tol= 0.3
Flow Tol Ratio= 0.001
Split Flow NTrial= 30
Split Flow Tol= 0.02
Split Flow Ratio= 0.02
Log Output Level= 0
Friction Slope Method= 1
Unsteady Friction Slope Method= 2
Unsteady Bridges Friction Slope Method= 1
Parabolic Critical Depth
Global Vel Dist=  1 , 1 , 1
Global Log Level= 0
CheckData=True
Encroach Param= -1, 0, 0, 0
BEGIN DESCRIPTION:
Multiple Run
END DESCRIPTION:

--- Stream0231.f01 (steady flow) ---

Flow Title=Multiple
Number of Profiles=7
Profile Names=10-year,25-year,50-year,1pct_min,100-year,1pct_plu,500-year
River Rch & RM= Stream0231,Reach-1,12449
     427     678     901     580    1157    2308    1883
River Rch & RM= Stream0231,Reach-1,10135
     947    1590    2191    1458    2909    5805    5071
River Rch & RM= Stream0231,Reach-1,4179
    1284    2193    3056    2054    4098    8177    7291
Boundary for River Rch & Prof#=Stream0231,Reach-1,1
Up Type=0
Dn Type=3
Dn Slope=0.005
Boundary for River Rch & Prof#=Stream0231,Reach-1,2
Up Type=0
Dn Type=3
Dn Slope=0.005
Boundary for River Rch & Prof#=Stream0231,Reach-1,3
Up Type=0
Dn Type=3
Dn Slope=0.005
Boundary for River Rch & Prof#=Stream0231,Reach-1,4
Up Type=0
Dn Type=3
Dn Slope=0.005
Boundary for River Rch & Prof#=Stream0231,Reach-1,5
Up Type=0
Dn Type=3
Dn Slope=0.005
Boundary for River Rch & Prof#=Stream0231,Reach-1,6
Up Type=0
Dn Type=3
Dn Slope=0.005
Boundary for River Rch & Prof#=Stream0231,Reach-1,7
Up Type=0
Dn Type=3
Dn Slope=0.005

--- Stream0231.g01 (geometry) ---

Geom Title=Existing Conditions

River Reach=Stream0231,Reach-1
Reach XY= 30
      1790375.00     13882125.00      1790282.81     13882228.21
      1790461.66     13882611.64      1790673.54     13882628.54
      1790972.71     13882869.15      1791580.93     13883122.76
      1791914.56     13883126.06      1792030.86     13883222.93
      1792254.97     13883224.94      1792576.47     13883028.55
      1792809.78     13883025.52      1793426.55     13883321.25
      1793714.50     13883326.22      1794074.99     13883467.47
      1794630.97     13883177.14      1794866.68     13883228.15
      1794938.62     13883388.21      1795272.57     13883719.48
      1795819.07     13883827.24      1796334.68     13884035.76
      1796469.17     13884172.70      1796808.29     13884858.37
      1797622.72     13885419.87      1797731.61     13885384.43
      1798076.55     13885621.25      1798954.95     13885725.59
      1799099.93     13885674.77      1799825.00     13885682.56
      1800249.92     13885825.20      1800625.00     13885725.00

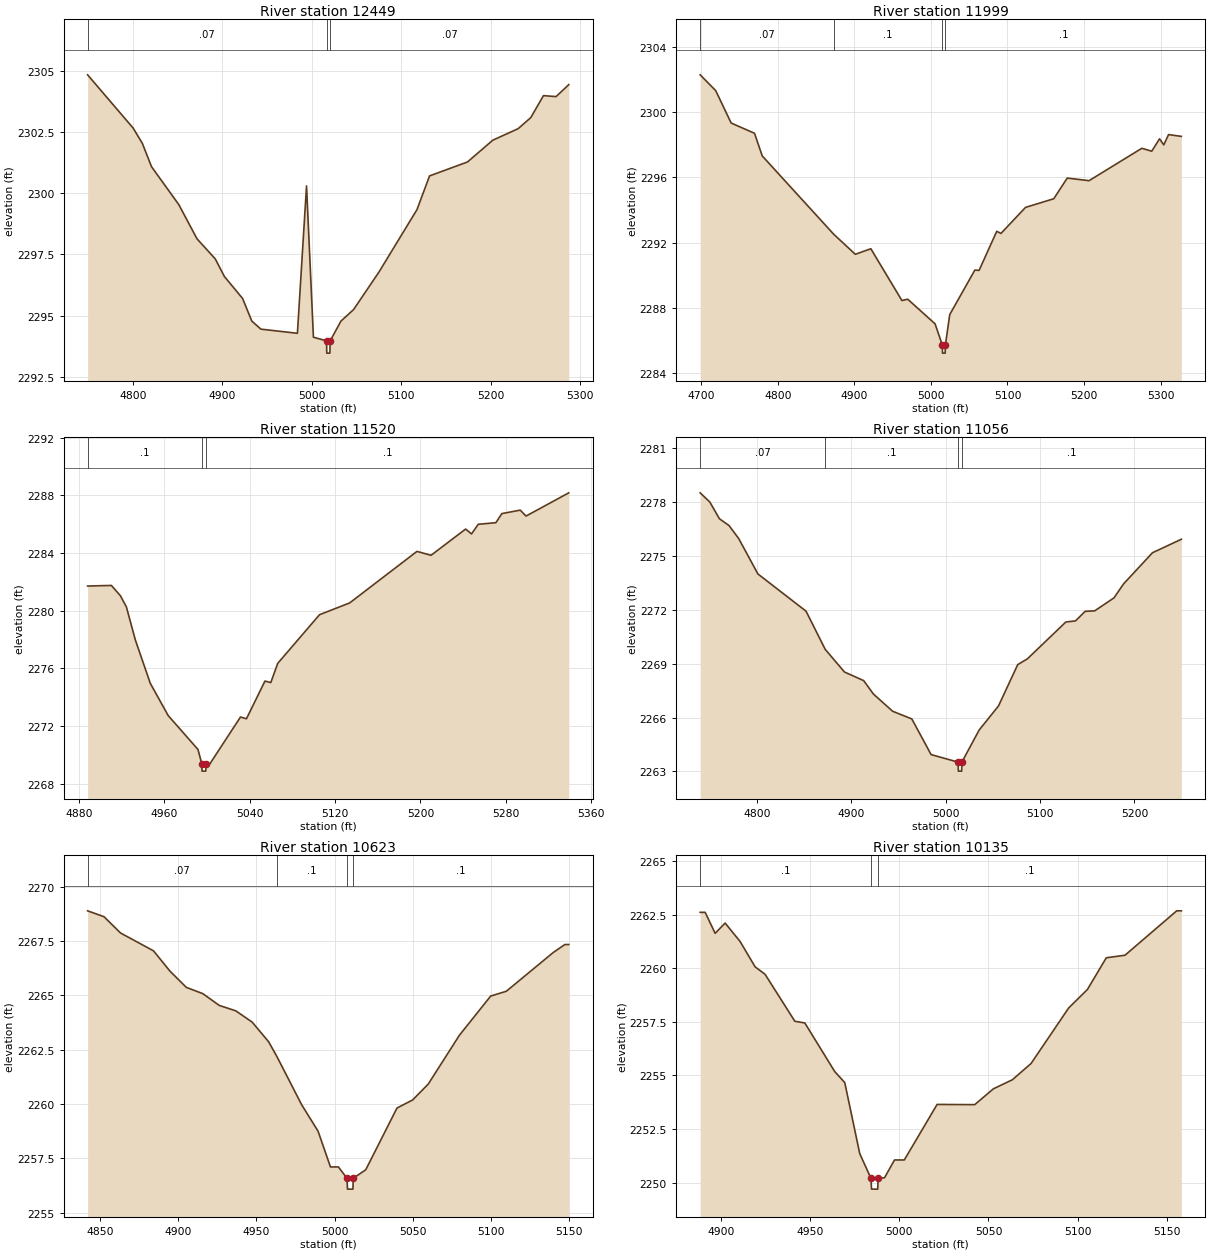
Type RM Length L Ch R = 1,12449,450,450,450
BEGIN DESCRIPTION:
Stream0231 26.0
END DESCRIPTION:
XS GIS Cut Line= 3
      1790075.03     13882324.99      1790325.00     13882275.00
      1790525.03     13882074.97
#Sta/Elev= 30
  4749.5 2304.84  4800.5 2302.66  4810.7 2302.04  4820.9 2301.09  4851.4 2299.54
  4871.8 2298.14  4892.2 2297.32  4902.4 2296.60  4922.8 2295.70  4933.0 2294.78
  4943.2 2294.45  4984.0 2294.28  4994.2 2300.30  5001.9 2294.12  5016.6 2293.97
  5016.8 2293.47  5020.3 2293.47  5020.6 2293.97  5032.7 2294.78  5046.8 2295.25
  5075.1 2296.78  5117.6 2299.33  5131.7 2300.71  5174.1 2301.28  5202.4 2302.17
  5230.7 2302.64  5244.8 2303.09  5259.0 2303.99  5273.1 2303.95  5287.3 2304.44
#Mann=3,-1,0
  4749.5    0.07       0  5016.6    0.05       0  5020.6    0.07       0
Bank Sta=5016.6,5020.6
Exp/Cntr=0.3,0.1

Type RM Length L Ch R = 1,11999,479,479,479
BEGIN DESCRIPTION:
Stream0231 25.0
END DESCRIPTION:
XS GIS Cut Line= 3
      1790225.01     13882675.00      1790525.00     13882625.00
      1790659.91     13882329.80
#Sta/Elev= 30
  4698.5 2302.30  4718.8 2301.33  4739.0 2299.34  4769.5 2298.71  4779.6 2297.32
  4873.0 2292.51  4901.2 2291.28  4921.5 2291.62  4962.1 2288.44  4969.7 2288.52
  5005.4 2287.01  5014.9 2285.71  5015.1 2285.21  5018.6 2285.21  5018.9 2285.71
  5024.6 2287.58  5057.4 2290.31  5062.9 2290.29  5086.0 2292.69  5091.5 2292.56
  5123.6 2294.16  5160.5 2294.69  5178.1 2295.96  5206.6 2295.80  5275.6 2297.79
  5288.5 2297.61  5298.7 2298.37  5304.2 2298.00  5310.5 2298.63  5327.2 2298.52
#Mann=4,-1,0
  4698.5    0.07       0  4873.0     0.1       0  5014.9    0.05       0
  5018.9     0.1       0
Bank Sta=5014.9,5018.9
Exp/Cntr=0.3,0.1

Type RM Length L Ch R = 1,11520,464,464,464
BEGIN DESCRIPTION:
Stream0231 24.0
END DESCRIPTION:
XS GIS Cut Line= 3
      1790825.01     13882874.99      1790925.00     13882825.00
      1791069.04     13882518.22
#Sta/Elev= 30
  4888.2 2281.71  4910.5 2281.75  4918.9 2281.04  4924.5 2280.27  4932.9 2277.98
  4946.9 2274.97  4963.7 2272.73  4991.6 2270.38  4995.2 2269.38  4995.4 2268.88
  4998.9 2268.88  4999.2 2269.38  5002.7 2269.38  5031.4 2272.63  5037.0 2272.51
  5054.3 2275.12  5059.8 2275.02  5066.3 2276.35  5105.4 2279.72  5133.7 2280.54
  5196.7 2284.11  5209.9 2283.84  5242.3 2285.66  5247.8 2285.32  5254.1 2285.99
  5270.6 2286.10  5276.2 2286.73  5293.4 2286.97  5298.9 2286.56  5338.9 2288.17
#Mann=3,-1,0
  4888.2     0.1       0  4995.2    0.05       0  4999.2     0.1       0
Bank Sta=4995.2,4999.2
Exp/Cntr=0.3,0.1

Type RM Length L Ch R = 1,11056,433,433,433
BEGIN DESCRIPTION:
Stream0231 23.0
END DESCRIPTION:
XS GIS Cut Line= 3
      1791275.00     13883274.98      1791325.00     13883025.00
      1791275.00     13882774.98
#Sta/Elev= 30
  4739.8 2278.49  4750.0 2277.98  4760.2 2277.05  4770.4 2276.67  4780.6 2275.95
  4801.0 2273.98  4852.0 2271.91  4872.3 2269.79  4892.7 2268.53  4913.1 2268.05
  4923.3 2267.31  4943.7 2266.35  4964.1 2265.92  4984.5 2263.94  5013.1 2263.52
  5013.4 2263.02  5016.9 2263.02  5017.1 2263.52  5035.5 2265.31  5055.9 2266.64
  5076.3 2268.94  5086.5 2269.26  5127.3 2271.31  5137.5 2271.37  5147.7 2271.90
  5157.9 2271.93  5178.3 2272.65  5188.5 2273.43  5219.1 2275.16  5249.7 2275.91
#Mann=4,-1,0
  4739.8    0.07       0  4872.3     0.1       0  5013.1    0.05       0
  5017.1     0.1       0
Bank Sta=5013.1,5017.1
Exp/Cntr=0.3,0.1

Type RM Length L Ch R = 1,10623,488,488,488
BEGIN DESCRIPTION:
Stream0231 22.0
END DESCRIPTION:
XS GIS Cut Line= 3
      1791675.00     13883275.00      1791725.00     13883125.00
      1791725.00     13882975.01
#Sta/Elev= 30
  4841.9 2268.89  4852.4 2268.62  4863.0 2267.87  4884.1 2267.05  4894.6 2266.12
  4905.1 2265.37  4915.7 2265.08  4926.2 2264.54  4936.8 2264.29  4947.3 2263.77
  4957.8 2262.87  4963.1 2262.19  4978.9 2259.98  4989.5 2258.75  4997.4 2257.11
  5002.5 2257.11  5008.0 2256.59  5008.3 2256.09  5011.8 2256.09  5012.0 2256.59
  5020.0 2256.98  5040.0 2259.82  5050.0 2260.19  5060.0 2260.92  5080.0 2263.17
  5100.0 2264.97  5110.0 2265.19  5140.0 2266.97  5147.5 2267.34  5150.0 2267.34
#Mann=4,-1,0
  4841.9    0.07       0  4963.1     0.1       0  5008.0    0.05       0
  5012.0     0.1       0
Bank Sta=5008,5012
Exp/Cntr=0.3,0.1

Type RM Length L Ch R = 1,10135,466,466,466
BEGIN DESCRIPTION:
Stream0231 21.0
END DESCRIPTION:
XS GIS Cut Line= 3
      1792124.99     13883325.02      1792175.00     13883225.00
      1792125.01     13883075.03
#Sta/Elev= 30
  4888.3 2262.61  4891.1 2262.61  4896.7 2261.63  4902.3 2262.11  4910.7 2261.25
  4919.1 2260.07  4924.7 2259.72  4941.4 2257.53  4947.0 2257.45  4963.8 2255.18
  4969.4 2254.67  4977.8 2251.36  4984.1 2250.20  4984.4 2249.70  4987.9 2249.70
  4988.1 2250.20  4991.7 2250.23  4997.3 2251.06  5002.8 2251.06  5021.2 2253.65
  5042.3 2253.64  5052.8 2254.38  5063.4 2254.80  5073.9 2255.56  5095.0 2258.15
  5105.5 2259.01  5116.1 2260.49  5126.6 2260.61  5155.6 2262.68  5158.2 2262.68
#Mann=3,-1,0
  4888.3     0.1       0  4984.1    0.05       0  4988.1     0.1       0
Bank Sta=4984.1,4988.1
Exp/Cntr=0.3,0.1

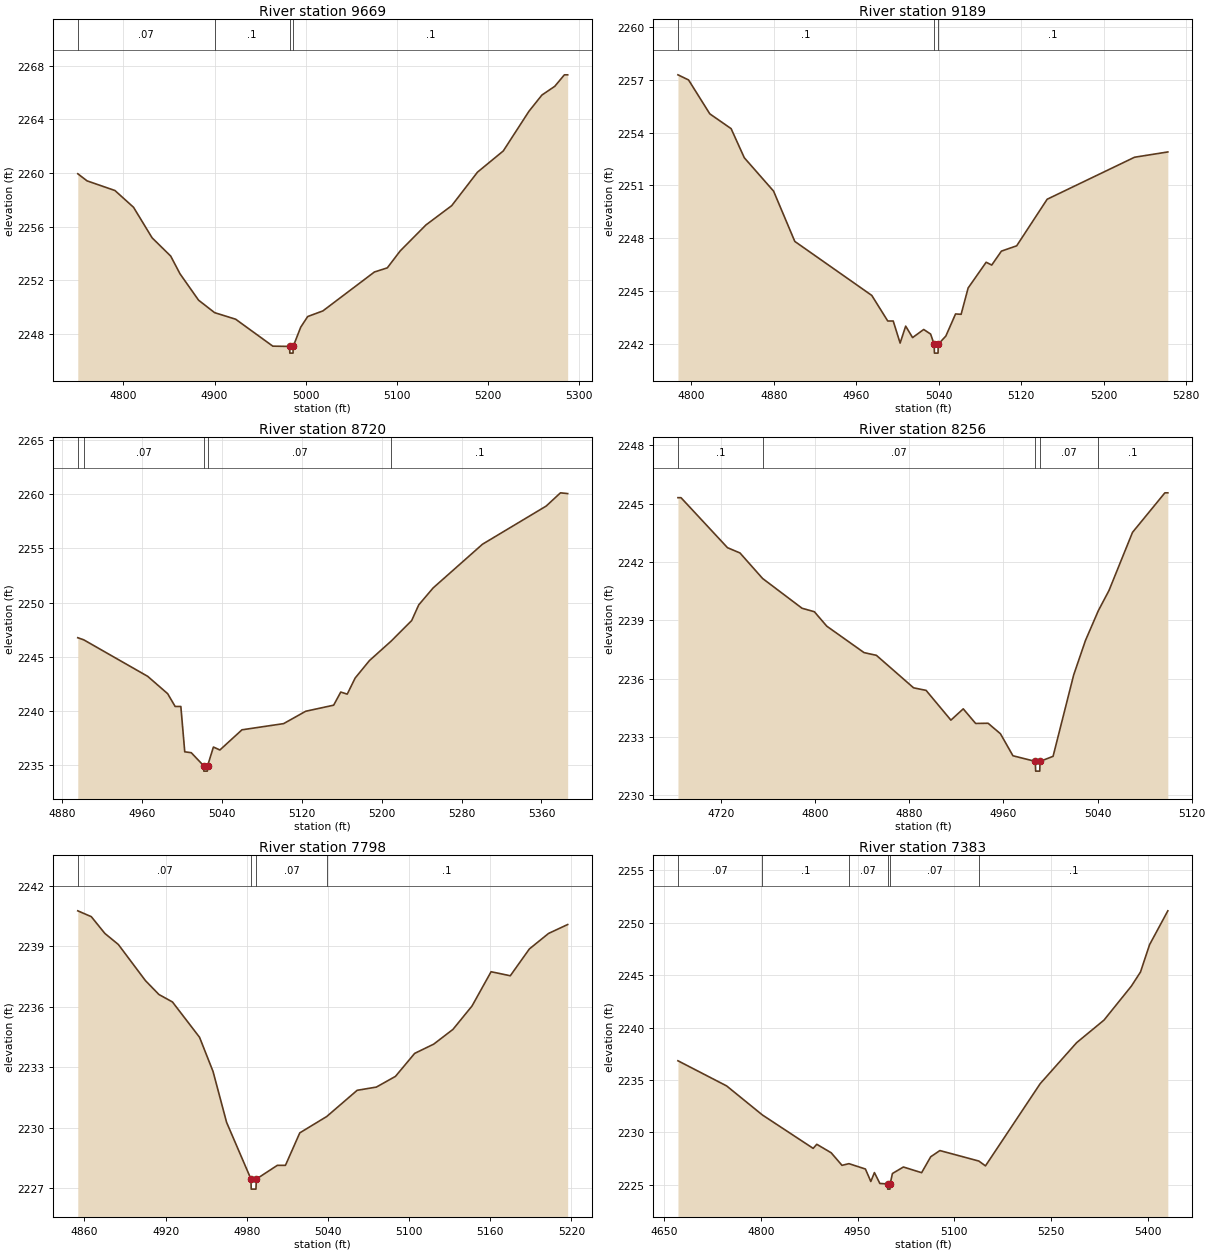
Type RM Length L Ch R = 1,9669,480,480,480
BEGIN DESCRIPTION:
Stream0231 20.0
END DESCRIPTION:
XS GIS Cut Line= 3
      1792525.00     13883274.98      1792575.00     13883025.00
      1792374.98     13882824.98
#Sta/Elev= 30
  4749.9 2259.94  4760.1 2259.41  4790.7 2258.69  4811.1 2257.44  4831.5 2255.16
  4851.9 2253.80  4862.1 2252.48  4882.5 2250.51  4900.1 2249.58  4923.2 2249.09
  4964.0 2247.08  4982.4 2247.06  4982.7 2246.56  4986.2 2246.56  4986.4 2247.06
  4994.6 2248.49  5002.3 2249.29  5019.0 2249.71  5075.5 2252.61  5089.7 2252.92
  5103.8 2254.18  5132.1 2256.12  5160.4 2257.56  5188.7 2260.06  5217.0 2261.64
  5245.2 2264.60  5259.4 2265.81  5273.5 2266.46  5284.1 2267.32  5287.7 2267.32
#Mann=4,-1,0
  4749.9    0.07       0  4900.1     0.1       0  4982.4    0.05       0
  4986.4     0.1       0
Bank Sta=4982.4,4986.4
Exp/Cntr=0.3,0.1

Type RM Length L Ch R = 1,9189,469,469,469
BEGIN DESCRIPTION:
Stream0231 19.0
END DESCRIPTION:
XS GIS Cut Line= 3
      1792975.00     13883325.02      1793025.00     13883125.00
      1792925.01     13882875.03
#Sta/Elev= 30
  4787.0 2257.27  4797.3 2256.98  4817.9 2255.06  4838.6 2254.22  4851.4 2252.57
  4879.8 2250.68  4900.4 2247.83  4975.1 2244.77  4990.6 2243.32  4995.9 2243.32
  5002.6 2242.07  5008.0 2243.03  5014.7 2242.38  5025.5 2242.84  5032.2 2242.58
  5035.6 2242.00  5035.9 2241.50  5039.4 2241.50  5039.6 2242.00  5047.0 2242.47
  5056.4 2243.72  5061.8 2243.70  5068.6 2245.19  5086.1 2246.65  5091.5 2246.49
  5100.9 2247.28  5115.7 2247.58  5145.3 2250.22  5230.1 2252.60  5262.4 2252.90
#Mann=3,-1,0
  4787.0     0.1       0  5035.6    0.05       0  5039.6     0.1       0
Bank Sta=5035.6,5039.6
Exp/Cntr=0.3,0.1

Type RM Length L Ch R = 1,8720,464,464,464
BEGIN DESCRIPTION:
Stream0231 18.0
END DESCRIPTION:
XS GIS Cut Line= 3
      1793425.00     13883424.97      1793425.00     13883325.00
      1793675.01     13883024.98
#Sta/Elev= 30
  4895.7 2246.76  4901.6 2246.57  4965.7 2243.20  4985.7 2241.60  4993.2 2240.42
  4998.9 2240.42  5002.8 2236.24  5009.3 2236.16  5021.7 2234.96  5021.9 2234.46
  5025.4 2234.46  5025.7 2234.96  5031.5 2236.68  5038.0 2236.41  5060.1 2238.27
  5101.8 2238.84  5123.9 2239.98  5151.9 2240.54  5159.0 2241.75  5165.5 2241.56
  5173.4 2243.04  5187.7 2244.65  5209.5 2246.45  5230.0 2248.34  5237.1 2249.79
  5251.5 2251.35  5300.9 2255.38  5364.7 2258.90  5379.0 2260.12  5386.2 2260.05
#Mann=5,-1,0
  4895.7     0.1       0  4901.6    0.07       0  5021.7    0.05       0
  5025.7    0.07       0  5209.5     0.1       0
Bank Sta=5021.7,5025.7
Exp/Cntr=0.3,0.1

Type RM Length L Ch R = 1,8256,458,458,458
BEGIN DESCRIPTION:
Stream0231 17.0
END DESCRIPTION:
XS GIS Cut Line= 3
      1793974.99     13883674.96      1793875.00     13883375.00
      1793875.00     13883274.99
#Sta/Elev= 30
  4683.5 2245.30  4686.1 2245.30  4725.6 2242.73  4736.2 2242.46  4755.4 2241.15
  4788.9 2239.62  4799.4 2239.44  4809.9 2238.70  4841.6 2237.34  4852.1 2237.20
  4883.7 2235.53  4894.3 2235.40  4915.4 2233.87  4925.9 2234.45  4936.4 2233.70
  4947.0 2233.71  4957.5 2233.17  4968.1 2232.04  4987.1 2231.75  4987.4 2231.25
  4990.9 2231.25  4991.1 2231.75  5002.2 2232.01  5019.7 2236.19  5029.7 2237.96
  5040.7 2239.50  5049.7 2240.53  5069.7 2243.52  5097.2 2245.55  5099.7 2245.55
#Mann=5,-1,0
  4683.5     0.1       0  4755.4    0.07       0  4987.1    0.05       0
  4991.1    0.07       0  5040.7     0.1       0
Bank Sta=4987.1,4991.1
Exp/Cntr=0.3,0.1

Type RM Length L Ch R = 1,7798,415,415,415
BEGIN DESCRIPTION:
Stream0231 16.0
END DESCRIPTION:
XS GIS Cut Line= 3
      1794275.00     13883524.97      1794275.00     13883375.00
      1794125.00     13883225.00
#Sta/Elev= 30
  4855.1 2240.76  4865.1 2240.47  4875.1 2239.64  4885.1 2239.09  4905.1 2237.30
  4915.1 2236.61  4925.1 2236.24  4945.1 2234.49  4955.1 2232.79  4965.1 2230.27
  4983.1 2227.46  4983.3 2226.96  4986.8 2226.96  4987.1 2227.46  5002.6 2228.14
  5008.6 2228.14  5019.2 2229.75  5039.1 2230.56  5061.6 2231.86  5075.8 2232.02
  5089.9 2232.55  5104.1 2233.69  5118.2 2234.15  5132.4 2234.88  5146.5 2236.04
  5160.6 2237.74  5174.8 2237.54  5188.9 2238.87  5203.1 2239.64  5217.2 2240.08
#Mann=4,-1,0
  4855.1    0.07       0  4983.1    0.05       0  4987.1    0.07       0
  5039.1     0.1       0
Bank Sta=4983.1,4987.1
Exp/Cntr=0.3,0.1

Type RM Length L Ch R = 1,7383,422,422,422
BEGIN DESCRIPTION:
Stream0231 15.0
END DESCRIPTION:
XS GIS Cut Line= 3
      1794474.99     13883475.03      1794625.00     13883175.00
      1794925.00     13882875.00
#Sta/Elev= 30
  4671.4 2236.83  4746.9 2234.43  4802.3 2231.66  4881.1 2228.47  4886.7 2228.86
  4909.0 2228.05  4925.8 2226.85  4936.6 2227.01  4962.1 2226.50  4970.5 2225.31
  4976.1 2226.16  4984.5 2225.12  4996.5 2225.08  4996.7 2224.58  5000.2 2224.58
  5000.5 2225.08  5004.0 2226.07  5021.0 2226.69  5049.3 2226.15  5063.4 2227.67
  5077.6 2228.26  5138.0 2227.26  5148.3 2226.80  5233.1 2234.64  5289.7 2238.56
  5332.1 2240.71  5374.5 2243.95  5388.7 2245.30  5402.8 2247.91  5431.1 2251.14
#Mann=6,-1,0
  4671.4    0.07       0  4802.3     0.1       0  4936.6    0.07       0
  4996.5    0.05       0  5000.5    0.07       0  5138.0     0.1       0
Bank Sta=4996.5,5000.5
Exp/Cntr=0.3,0.1

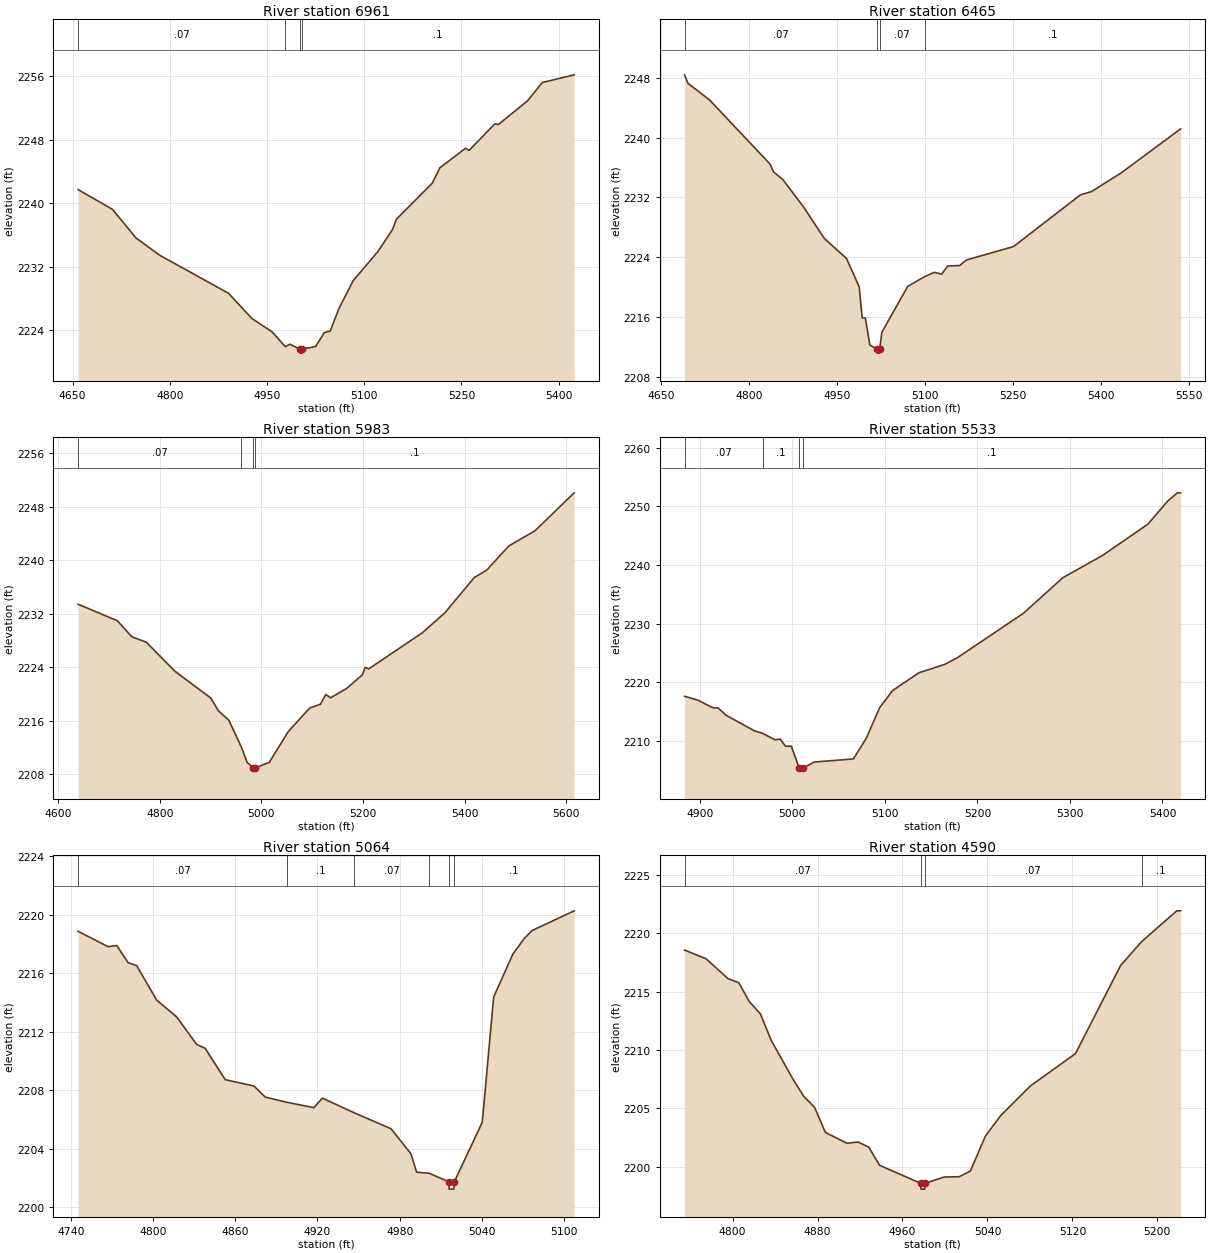
Type RM Length L Ch R = 1,6961,496,496,496
BEGIN DESCRIPTION:
Stream0231 14.0
END DESCRIPTION:
XS GIS Cut Line= 3
      1794775.02     13883674.97      1794925.00     13883375.00
      1795112.68     13882988.20
#Sta/Elev= 30
  4658.5 2241.70  4711.6 2239.21  4747.9 2235.61  4784.2 2233.44  4890.5 2228.65
  4926.8 2225.46  4957.5 2223.81  4978.3 2221.92  4985.5 2222.24  5000.4 2221.61
  5000.6 2221.11  5004.1 2221.11  5004.4 2221.61  5024.9 2221.94  5038.3 2223.69
  5047.5 2223.89  5060.6 2226.67  5082.8 2230.22  5120.8 2233.88  5143.4 2236.64
  5149.5 2237.96  5205.1 2242.52  5216.6 2244.44  5256.2 2246.90  5261.8 2246.64
  5301.3 2249.97  5306.9 2249.89  5352.0 2252.88  5374.6 2255.18  5423.8 2256.15
#Mann=4,-1,0
  4658.5    0.07       0  4978.3     0.1       0  5000.4    0.05       0
  5004.4     0.1       0
Bank Sta=5000.4,5004.4
Exp/Cntr=0.3,0.1

Type RM Length L Ch R = 1,6465,482,482,482
BEGIN DESCRIPTION:
Stream0231 13.0
END DESCRIPTION:
XS GIS Cut Line= 3
      1795125.56     13883992.00      1795275.00     13883725.00
      1795385.48     13883195.89
#Sta/Elev= 30
  4690.0 2248.41  4695.7 2247.28  4732.4 2245.07  4835.5 2236.50  4841.8 2235.43
  4857.8 2234.39  4892.8 2230.76  4928.6 2226.51  4966.3 2223.85  4988.0 2220.05
  4993.1 2215.89  4998.5 2215.89  5006.2 2212.27  5019.0 2211.68  5019.2 2211.18
  5022.7 2211.18  5023.0 2211.68  5026.6 2213.96  5071.0 2220.13  5099.5 2221.40
  5115.9 2221.99  5128.8 2221.75  5139.0 2222.84  5159.4 2222.90  5171.0 2223.64
  5251.4 2225.44  5365.9 2232.37  5384.2 2232.78  5435.3 2235.30  5536.5 2241.18
#Mann=4,-1,0
  4690.0    0.07       0  5019.0    0.05       0  5023.0    0.07       0
  5099.5     0.1       0
Bank Sta=5019,5023
Exp/Cntr=0.3,0.1

Type RM Length L Ch R = 1,5983,450,450,450
BEGIN DESCRIPTION:
Stream0231 12.0
END DESCRIPTION:
XS GIS Cut Line= 3
      1795489.06     13884097.96      1795725.00     13883825.00
      1795922.67     13883242.11
#Sta/Elev= 30
  4639.2 2233.42  4716.5 2230.95  4745.0 2228.55  4773.5 2227.75  4829.5 2223.43
  4900.7 2219.39  4915.0 2217.53  4935.9 2216.10  4960.0 2212.18  4972.0 2209.79
  4984.3 2209.00  4984.5 2208.50  4988.3 2209.00  5015.7 2209.82  5052.8 2214.40
  5095.0 2217.92  5116.2 2218.49  5126.7 2219.95  5136.1 2219.45  5167.5 2220.83
  5198.9 2222.89  5204.2 2224.00  5211.2 2223.76  5316.8 2229.16  5361.2 2232.14
  5418.7 2237.39  5443.5 2238.51  5486.8 2242.11  5538.5 2244.39  5615.5 2250.05
#Mann=4,-1,0
  4639.2    0.07       0  4960.0     0.1       0  4984.3    0.05       0
  4988.3     0.1       0
Bank Sta=4984.3,4988.3
Exp/Cntr=0.3,0.1

Type RM Length L Ch R = 1,5533,469,469,469
BEGIN DESCRIPTION:
Stream0231 11.0
END DESCRIPTION:
XS GIS Cut Line= 3
      1796075.02     13884074.97      1796125.00     13883975.00
      1796424.98     13883675.02
#Sta/Elev= 30
  4883.6 2217.63  4897.5 2217.01  4914.3 2215.68  4919.9 2215.64  4928.3 2214.42
  4959.0 2211.76  4968.2 2211.30  4981.4 2210.22  4987.0 2210.34  4992.6 2209.13
  4998.9 2209.13  5007.5 2205.38  5007.8 2204.88  5011.3 2204.88  5011.5 2205.38
  5023.6 2206.43  5066.1 2206.96  5080.2 2210.56  5094.4 2215.71  5108.5 2218.63
  5136.8 2221.64  5165.1 2223.10  5179.2 2224.29  5249.9 2231.80  5292.3 2237.84
  5334.8 2241.60  5384.3 2246.97  5405.5 2250.88  5416.1 2252.31  5419.6 2252.31
#Mann=4,-1,0
  4883.6    0.07       0  4968.2     0.1       0  5007.5    0.05       0
  5011.5     0.1       0
Bank Sta=5007.5,5011.5
Exp/Cntr=0.3,0.1

Type RM Length L Ch R = 1,5064,474,474,474
BEGIN DESCRIPTION:
Stream0231 10.0
END DESCRIPTION:
XS GIS Cut Line= 3
      1796274.98     13884375.02      1796475.00     13884225.00
      1796574.97     13884175.02
#Sta/Elev= 30
  4745.4 2218.86  4767.3 2217.81  4773.6 2217.89  4781.9 2216.71  4788.1 2216.52
  4802.7 2214.16  4817.3 2213.01  4831.9 2211.13  4838.1 2210.86  4852.7 2208.72
  4873.6 2208.29  4881.9 2207.53  4897.5 2207.18  4917.3 2206.81  4923.6 2207.46
  4946.7 2206.46  4973.6 2205.37  4988.1 2203.67  4992.3 2202.40  5001.6 2202.32
  5015.8 2201.74  5016.0 2201.24  5019.5 2201.24  5019.8 2201.74  5040.2 2205.81
  5048.5 2214.37  5062.5 2217.30  5070.9 2218.38  5076.5 2218.91  5107.2 2220.26
#Mann=6,-1,0
  4745.4    0.07       0  4897.5     0.1       0  4946.7    0.07       0
  5001.6     0.1       0  5015.8    0.05       0  5019.8     0.1       0
Bank Sta=5015.8,5019.8
Exp/Cntr=0.3,0.1

Type RM Length L Ch R = 1,4590,411,411,411
BEGIN DESCRIPTION:
Stream0231 9.0
END DESCRIPTION:
XS GIS Cut Line= 3
      1796625.00     13884874.99      1796675.00     13884625.00
      1796825.02     13884474.98
#Sta/Elev= 30
  4754.8 2218.55  4775.2 2217.79  4795.6 2216.11  4805.8 2215.75  4816.0 2214.11
  4826.2 2213.09  4836.4 2210.82  4856.8 2207.52  4867.0 2206.04  4877.2 2205.10
  4887.4 2202.95  4907.8 2202.02  4918.0 2202.13  4928.2 2201.70  4938.4 2200.14
  4977.1 2198.60  4977.4 2198.10  4980.9 2198.10  4981.1 2198.60  4999.5 2199.14
  5013.3 2199.16  5023.9 2199.64  5038.0 2202.62  5052.2 2204.36  5080.4 2206.92
  5122.9 2209.69  5165.3 2217.21  5185.1 2219.26  5218.3 2221.90  5221.9 2221.90
#Mann=4,-1,0
  4754.8    0.07       0  4977.1    0.05       0  4981.1    0.07       0
  5185.1     0.1       0
Bank Sta=4977.1,4981.1
Exp/Cntr=0.3,0.1

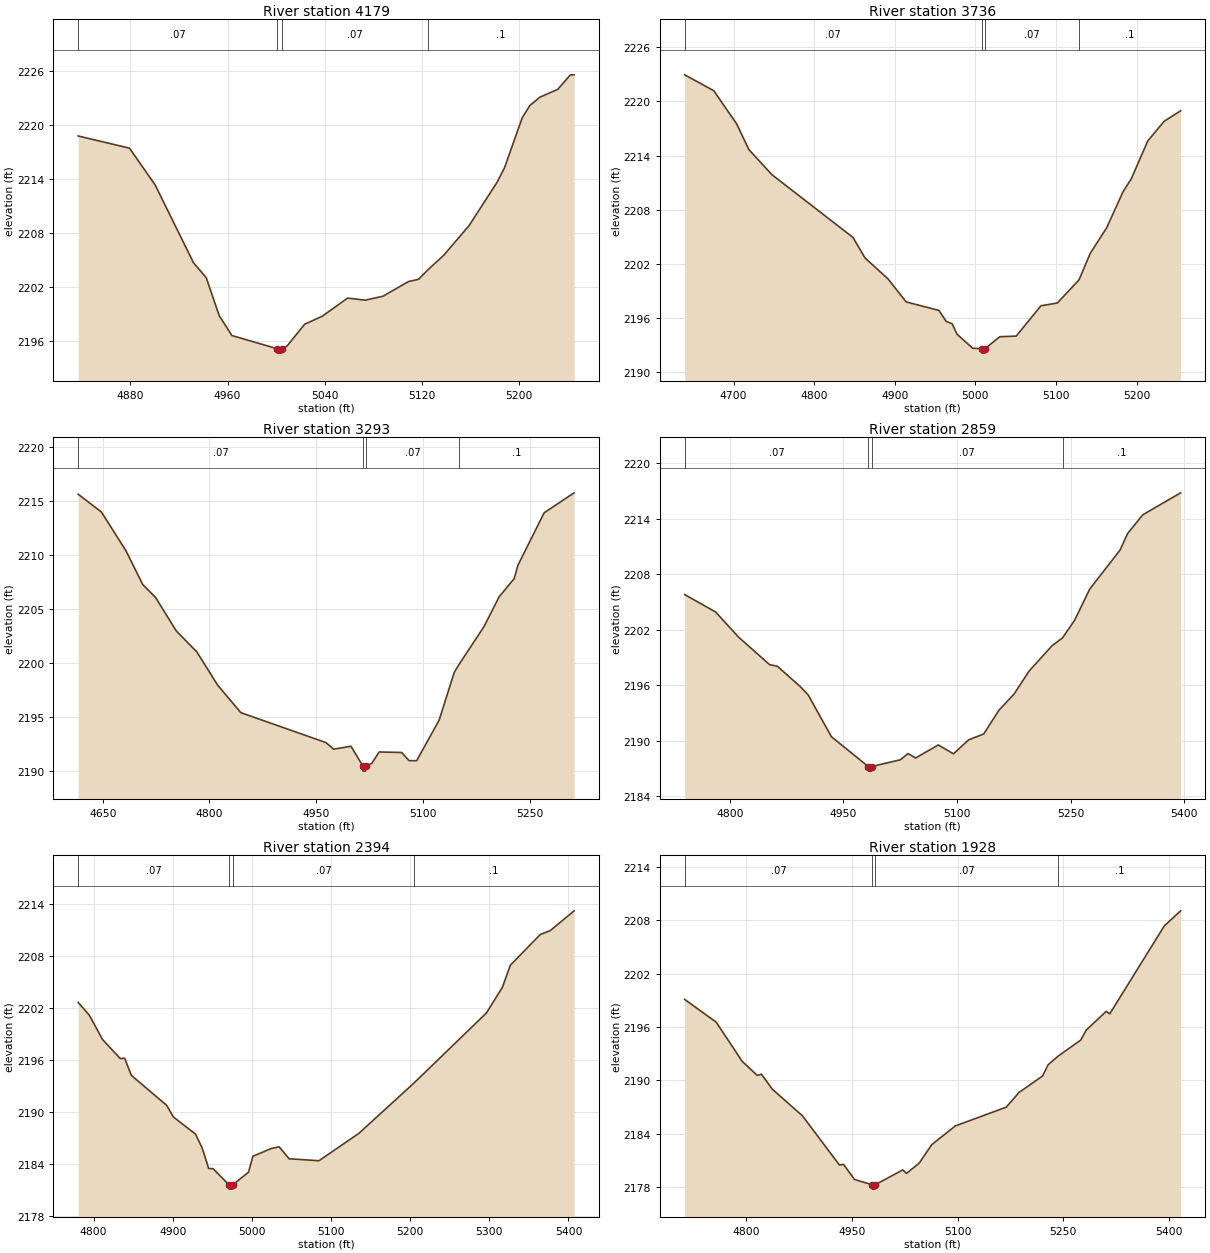
Type RM Length L Ch R = 1,4179,443,443,443
BEGIN DESCRIPTION:
Stream0231 8.0
END DESCRIPTION:
XS GIS Cut Line= 3
      1796774.98     13884975.01      1796925.00     13884925.00
      1797074.98     13884725.03
#Sta/Elev= 30
  4837.1 2218.76  4879.3 2217.41  4900.4 2213.34  4932.0 2204.70  4942.5 2203.04
  4953.1 2198.85  4963.6 2196.64  5000.5 2195.19  5000.8 2194.69  5004.3 2194.69
  5004.5 2195.19  5008.8 2195.45  5023.4 2197.89  5037.9 2198.78  5058.8 2200.79
  5073.4 2200.56  5087.9 2201.00  5108.8 2202.62  5117.1 2202.87  5125.1 2203.96
  5137.9 2205.54  5158.8 2208.84  5181.7 2213.61  5187.9 2215.24  5202.5 2220.79
  5208.8 2222.15  5217.1 2223.07  5231.7 2223.93  5242.1 2225.54  5245.2 2225.54
#Mann=4,-1,0
  4837.1    0.07       0  5000.5    0.05       0  5004.5    0.07       0
  5125.1     0.1       0
Bank Sta=5000.5,5004.5
Exp/Cntr=0.3,0.1

Type RM Length L Ch R = 1,3736,443,443,443
BEGIN DESCRIPTION:
Stream0231 7.0
END DESCRIPTION:
XS GIS Cut Line= 3
      1796975.00     13885375.00      1797275.00     13885175.00
      1797325.00     13884925.00
#Sta/Elev= 30
  4639.2 2222.95  4675.3 2221.19  4703.8 2217.50  4718.8 2214.67  4747.4 2211.88
  4848.0 2204.92  4863.0 2202.64  4891.6 2200.31  4914.1 2197.76  4954.7 2196.82
  4963.7 2195.61  4971.2 2195.33  4977.2 2194.18  4996.7 2192.62  5007.9 2192.58
  5008.1 2192.08  5011.7 2192.08  5012.0 2192.58  5030.3 2193.90  5050.7 2193.97
  5081.3 2197.33  5101.7 2197.64  5128.7 2200.22  5142.5 2203.14  5162.9 2205.98
  5183.3 2209.99  5193.5 2211.42  5213.9 2215.61  5234.3 2217.80  5254.7 2218.96
#Mann=4,-1,0
  4639.2    0.07       0  5007.9    0.05       0  5012.0    0.07       0
  5128.7     0.1       0
Bank Sta=5007.9,5012
Exp/Cntr=0.3,0.1

Type RM Length L Ch R = 1,3293,434,434,434
BEGIN DESCRIPTION:
Stream0231 6.0
END DESCRIPTION:
XS GIS Cut Line= 3
      1797275.00     13885575.00      1797625.00     13885425.00
      1797724.99     13885125.02
#Sta/Elev= 30
  4615.6 2215.66  4648.2 2214.01  4682.7 2210.41  4706.3 2207.28  4724.4 2206.07
  4753.4 2202.97  4782.4 2201.01  4811.4 2197.95  4844.1 2195.38  4963.8 2192.60
  4974.6 2191.99  4999.0 2192.26  5015.4 2190.45  5015.7 2189.95  5019.3 2189.95
  5019.5 2190.45  5028.0 2190.65  5038.6 2191.73  5070.2 2191.68  5080.7 2190.92
  5091.3 2190.92  5122.9 2194.69  5144.0 2199.10  5151.0 2199.87  5186.1 2203.39
  5207.2 2206.14  5228.3 2207.82  5233.6 2209.07  5270.5 2213.94  5312.6 2215.79
#Mann=4,-1,0
  4615.6    0.07       0  5015.4    0.05       0  5019.5    0.07       0
  5151.0     0.1       0
Bank Sta=5015.4,5019.5
Exp/Cntr=0.3,0.1

Type RM Length L Ch R = 1,2859,465,465,465
BEGIN DESCRIPTION:
Stream0231 5.0
END DESCRIPTION:
XS GIS Cut Line= 3
      1797925.00     13885825.02      1797975.00     13885575.00
      1797975.00     13885174.97
#Sta/Elev= 30
  4740.3 2205.79  4781.1 2203.91  4811.7 2201.17  4852.5 2198.21  4862.7 2198.04
  4893.3 2195.82  4903.5 2194.93  4934.1 2190.42  4982.7 2187.20  4983.1 2186.70
  4987.1 2186.70  4987.4 2187.20  5025.3 2187.93  5035.3 2188.60  5045.3 2188.12
  5075.3 2189.53  5095.3 2188.57  5115.3 2190.08  5135.3 2190.72  5155.3 2193.28
  5175.3 2195.03  5195.3 2197.53  5225.3 2200.24  5239.3 2201.11  5255.3 2203.01
  5275.3 2206.39  5315.3 2210.60  5325.3 2212.39  5345.3 2214.41  5395.3 2216.79
#Mann=4,-1,0
  4740.3    0.07       0  4982.7    0.05       0  4987.4    0.07       0
  5239.3     0.1       0
Bank Sta=4982.7,4987.4
Exp/Cntr=0.3,0.1

Type RM Length L Ch R = 1,2394,466,466,466
BEGIN DESCRIPTION:
Stream0231 4.0
END DESCRIPTION:
XS GIS Cut Line= 3
      1798324.99     13885825.01      1798425.00     13885625.00
      1798475.00     13885225.03
#Sta/Elev= 30
  4780.5 2202.64  4794.5 2201.17  4811.3 2198.36  4833.6 2196.17  4839.2 2196.21
  4847.6 2194.24  4892.3 2190.78  4900.7 2189.45  4928.7 2187.47  4937.0 2185.90
  4945.4 2183.51  4951.0 2183.48  4971.0 2181.63  4971.3 2181.13  4975.4 2181.13
  4975.8 2181.63  4995.7 2183.08  5001.3 2184.92  5024.3 2185.80  5034.4 2186.01
  5047.0 2184.63  5084.7 2184.40  5135.1 2187.55  5204.9 2193.36  5296.4 2201.43
  5316.5 2204.37  5326.6 2206.93  5364.4 2210.46  5377.0 2210.91  5407.2 2213.19
#Mann=4,-1,0
  4780.5    0.07       0  4971.0    0.05       0  4975.8    0.07       0
  5204.9     0.1       0
Bank Sta=4971,4975.8
Exp/Cntr=0.3,0.1

Type RM Length L Ch R = 1,1928,449,449,449
BEGIN DESCRIPTION:
Stream0231 3.0
END DESCRIPTION:
XS GIS Cut Line= 3
      1798724.99     13885925.02      1798875.00     13885675.00
      1798775.00     13885274.99
#Sta/Elev= 30
  4712.6 2199.11  4757.3 2196.55  4794.3 2192.13  4815.6 2190.55  4821.5 2190.69
  4837.0 2189.00  4879.8 2186.00  4932.3 2180.46  4938.1 2180.54  4953.6 2178.84
  4978.5 2178.25  4978.8 2177.75  4982.9 2177.75  4983.3 2178.25  5022.2 2179.92
  5027.4 2179.52  5045.4 2180.67  5063.4 2182.77  5096.9 2184.87  5169.1 2186.98
  5187.1 2188.63  5220.6 2190.49  5228.4 2191.74  5242.6 2192.72  5274.8 2194.53
  5282.5 2195.65  5310.8 2197.76  5316.0 2197.49  5393.3 2207.38  5416.5 2209.08
#Mann=4,-1,0
  4712.6    0.07       0  4978.5    0.05       0  4983.3    0.07       0
  5242.6     0.1       0
Bank Sta=4978.5,4983.3
Exp/Cntr=0.3,0.1

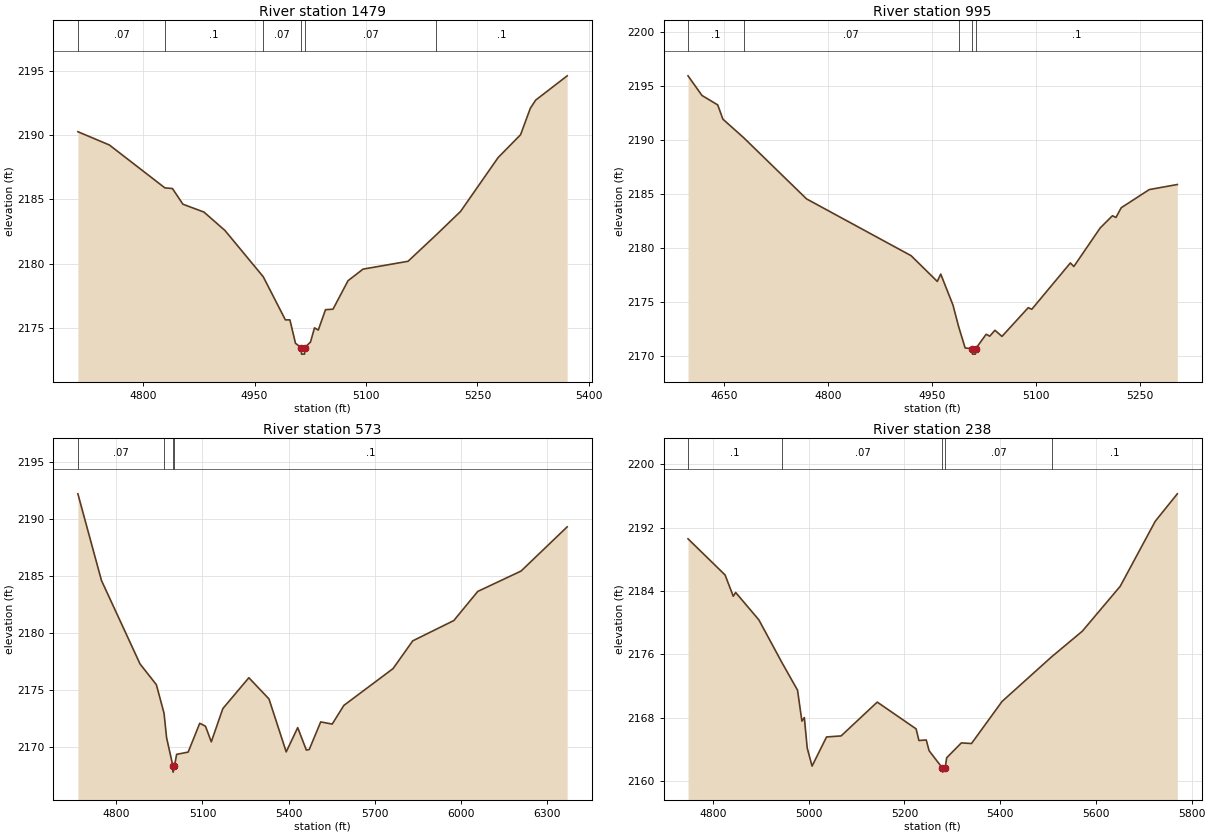
Type RM Length L Ch R = 1,1479,484,484,484
BEGIN DESCRIPTION:
Stream0231 2.0
END DESCRIPTION:
XS GIS Cut Line= 3
      1799075.01     13885924.99      1799275.00     13885725.00
      1799222.82     13885352.87
#Sta/Elev= 30
  4712.2 2190.26  4754.6 2189.23  4829.3 2185.90  4839.5 2185.85  4853.6 2184.63
  4881.9 2184.02  4910.2 2182.59  4961.7 2179.00  4991.5 2175.65  4997.6 2175.65
  5005.1 2173.83  5012.8 2173.49  5013.2 2172.99  5017.3 2172.99  5017.6 2173.49
  5025.3 2173.93  5030.7 2175.03  5035.8 2174.86  5045.5 2176.44  5055.6 2176.48
  5075.8 2178.69  5096.0 2179.59  5156.6 2180.20  5194.9 2182.27  5227.3 2184.07
  5277.8 2188.25  5308.1 2190.03  5321.2 2192.08  5328.3 2192.71  5370.8 2194.60
#Mann=6,-1,0
  4712.2    0.07       0  4829.3     0.1       0  4961.7    0.07       0
  5012.8    0.05       0  5017.6    0.07       0  5194.9     0.1       0
Bank Sta=5012.8,5017.6
Exp/Cntr=0.3,0.1

Type RM Length L Ch R = 1,995,422,422,422
BEGIN DESCRIPTION:
Stream0231 1.0
END DESCRIPTION:
XS GIS Cut Line= 3
      1799675.00     13886125.02      1799725.00     13885725.00
      1799675.00     13885424.98
#Sta/Elev= 30
  4597.3 2195.97  4617.5 2194.15  4640.2 2193.28  4647.7 2191.96  4677.8 2190.24
  4768.6 2184.58  4919.8 2179.32  4957.6 2176.94  4962.6 2177.62  4980.3 2174.75
  4988.5 2172.75  4997.9 2170.78  5008.1 2170.71  5008.4 2170.21  5012.7 2170.21
  5013.1 2170.71  5028.3 2172.05  5033.4 2171.87  5041.0 2172.42  5051.1 2171.85
  5089.1 2174.51  5094.2 2174.36  5150.0 2178.65  5155.0 2178.32  5193.1 2181.89
  5210.8 2183.02  5215.9 2182.86  5223.5 2183.76  5264.0 2185.44  5304.6 2185.91
#Mann=5,-1,0
  4597.3     0.1       0  4677.8    0.07       0  4988.5     0.1       0
  5008.1    0.05       0  5013.1     0.1       0
Bank Sta=5008.1,5013.1
Exp/Cntr=0.3,0.1

Type RM Length L Ch R = 1,573,335,335,335
BEGIN DESCRIPTION:
Stream0231 0.0
END DESCRIPTION:
XS GIS Cut Line= 4
      1800067.26     13886106.60      1800129.27     13885524.43
      1800134.16     13885214.85      1799793.00     13884483.05
#Sta/Elev= 30
  4666.5 2192.20  4748.6 2184.59  4882.8 2177.26  4939.6 2175.44  4966.3 2172.93
  4975.2 2170.78  4997.5 2168.26  4997.8 2167.76  5002.5 2168.26  5010.0 2169.32
  5050.3 2169.52  5090.5 2172.05  5110.6 2171.79  5130.7 2170.42  5170.9 2173.34
  5261.4 2176.05  5331.4 2174.19  5391.4 2169.54  5431.4 2171.67  5461.4 2169.70
  5471.4 2169.74  5511.4 2172.17  5551.4 2171.98  5592.0 2173.62  5763.1 2176.85
  5831.7 2179.29  5974.5 2181.07  6057.9 2183.63  6208.6 2185.42  6369.0 2189.30
#Mann=4,-1,0
  4666.5    0.07       0  4966.3     0.1       0  4997.5    0.05       0
  5002.5     0.1       0
Bank Sta=4997.5,5002.5
Exp/Cntr=0.3,0.1

Type RM Length L Ch R = 1,238,0,0,0
BEGIN DESCRIPTION:
Stream0231 0.1
END DESCRIPTION:
XS GIS Cut Line= 3
      1800386.76     13886071.64      1800436.24     13885714.85
      1800785.22     13885152.32
#Sta/Elev= 30
  4747.9 2190.58  4825.3 2186.02  4842.4 2183.33  4847.4 2183.81  4895.9 2180.35
  4944.8 2174.88  4976.7 2171.47  4985.8 2167.57  4990.9 2168.02  4996.9 2164.18
  5007.0 2161.89  5037.3 2165.57  5067.7 2165.70  5143.2 2169.97  5224.4 2166.59
  5230.3 2165.12  5245.6 2165.19  5251.5 2163.84  5279.5 2161.63  5279.9 2161.13
  5285.1 2161.63  5288.2 2162.94  5318.9 2164.82  5340.1 2164.74  5403.9 2170.05
  5507.4 2175.68  5571.6 2178.92  5650.8 2184.59  5724.0 2192.80  5770.1 2196.26
#Mann=5,-1,0
  4747.9     0.1       0  4944.8    0.07       0  5279.5    0.05       0
  5285.1    0.07       0  5507.4     0.1       0
Bank Sta=5279.5,5285.1
Exp/Cntr=0.3,0.1

Chan Stop Cuts=-1