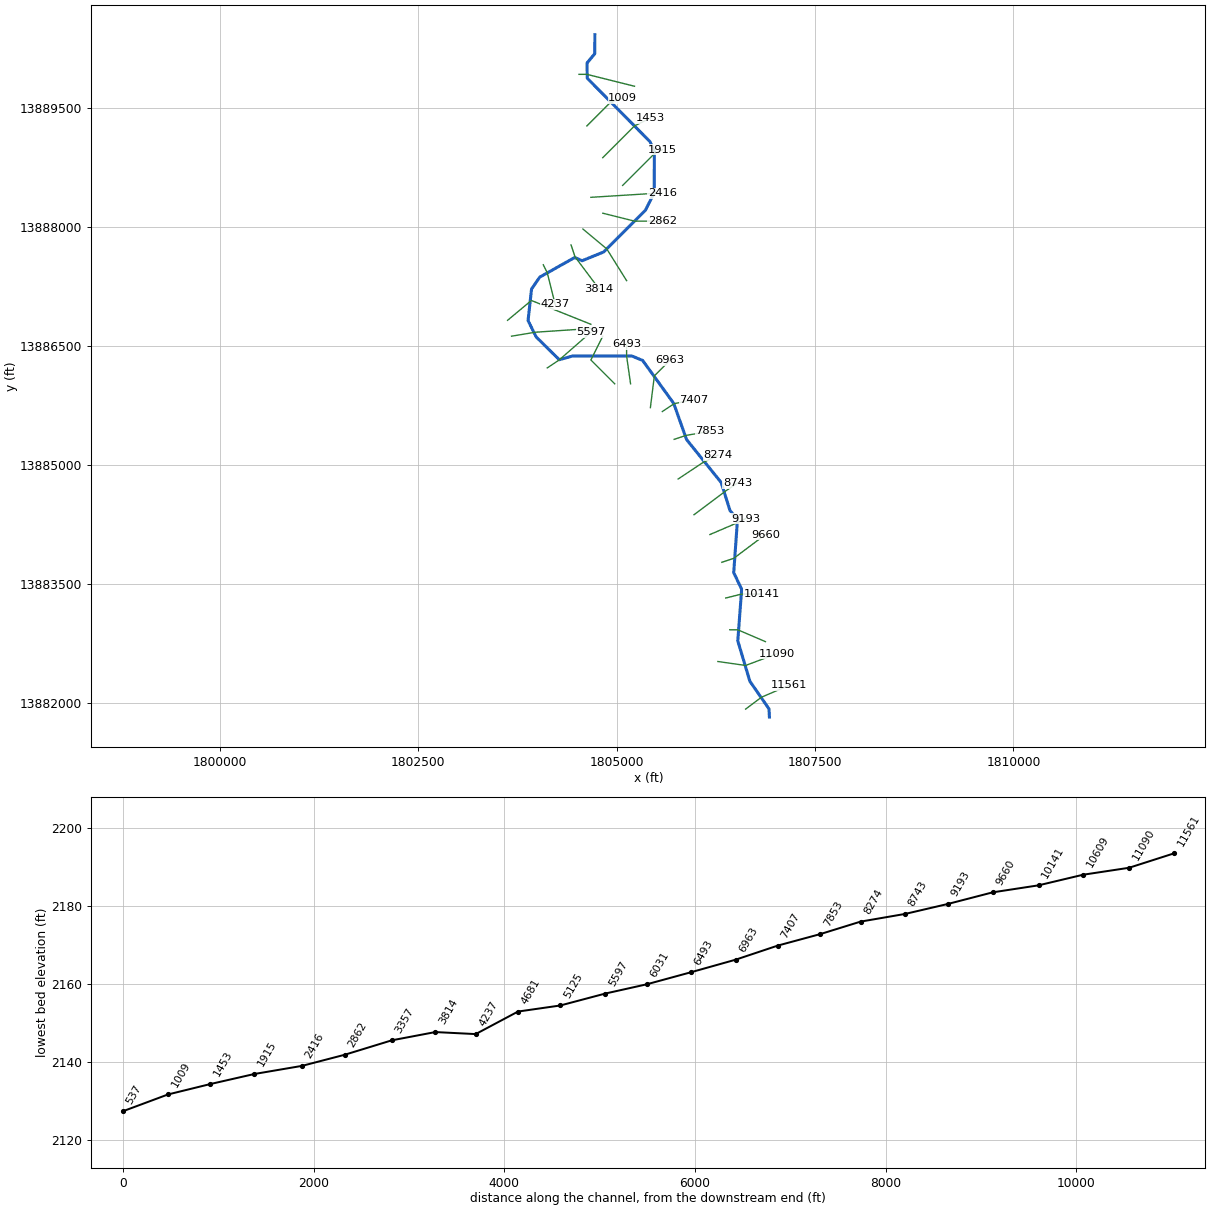
--- Stream0233.prj (project) ---

Proj Title=Stream0233 Base Level Engineering
Current Plan=p01
Default Exp/Contr=0.3,0.1
English Units
Geom File=g01
Flow File=f01
Plan File=p01
BEGIN DESCRIPTION:
Stream0233
END DESCRIPTION:

--- Stream0233.p01 (plan) ---

Plan Title=Multiple Run
Short Identifier=Multiple
Geom File=g01
Flow File=f01
Subcritical Flow
K Sum by GR= 0
Std Step Tol= 0.01
Critical Tol= 0.01
Num of Std Step Trials= 20
Max Error Tol= 0.3
Flow Tol Ratio= 0.001
Split Flow NTrial= 30
Split Flow Tol= 0.02
Split Flow Ratio= 0.02
Log Output Level= 0
Friction Slope Method= 1
Unsteady Friction Slope Method= 2
Unsteady Bridges Friction Slope Method= 1
Parabolic Critical Depth
Global Vel Dist=  1 , 1 , 1
Global Log Level= 0
CheckData=True
Encroach Param= -1, 0, 0, 0
BEGIN DESCRIPTION:
Multiple Run
END DESCRIPTION:

--- Stream0233.f01 (steady flow) ---

Flow Title=Multiple
Number of Profiles=7
Profile Names=10-year,25-year,50-year,1pct_min,100-year,1pct_plu,500-year
River Rch & RM= Stream0233,Reach-1,11561
    1654    2868    4035    2737    5461   10896    9899
River Rch & RM= Stream0233,Reach-1,7407
    1894    3295    4648    3157    6299   12568   11456
Boundary for River Rch & Prof#=Stream0233,Reach-1,1
Up Type=0
Dn Type=3
Dn Slope=0.005
Boundary for River Rch & Prof#=Stream0233,Reach-1,2
Up Type=0
Dn Type=3
Dn Slope=0.005
Boundary for River Rch & Prof#=Stream0233,Reach-1,3
Up Type=0
Dn Type=3
Dn Slope=0.005
Boundary for River Rch & Prof#=Stream0233,Reach-1,4
Up Type=0
Dn Type=3
Dn Slope=0.005
Boundary for River Rch & Prof#=Stream0233,Reach-1,5
Up Type=0
Dn Type=3
Dn Slope=0.005
Boundary for River Rch & Prof#=Stream0233,Reach-1,6
Up Type=0
Dn Type=3
Dn Slope=0.005
Boundary for River Rch & Prof#=Stream0233,Reach-1,7
Up Type=0
Dn Type=3
Dn Slope=0.005

--- Stream0233.g01 (geometry) ---

Geom Title=Existing Conditions

River Reach=Stream0233,Reach-1
Reach XY= 30
      1806925.00     13881825.00      1806919.64     13881927.49
      1806678.62     13882276.50      1806526.20     13882785.51
      1806575.46     13883435.19      1806475.06     13883645.03
      1806522.93     13884319.14      1806428.62     13884426.50
      1806316.86     13884781.06      1805880.52     13885322.57
      1805719.15     13885777.29      1805327.30     13886319.17
      1805190.18     13886375.44      1804445.18     13886375.28
      1804276.50     13886328.46      1803985.76     13886615.32
      1803883.04     13886821.68      1803927.06     13887219.15
      1804030.61     13887369.41      1804471.69     13887616.93
      1804564.29     13887575.81      1804834.68     13887685.76
      1805361.60     13888211.70      1805472.93     13888430.86
      1805474.94     13888954.98      1805419.24     13889077.53
      1804628.53     13889876.46      1804627.06     13890069.14
      1804723.95     13890185.44      1804725.00     13890425.00

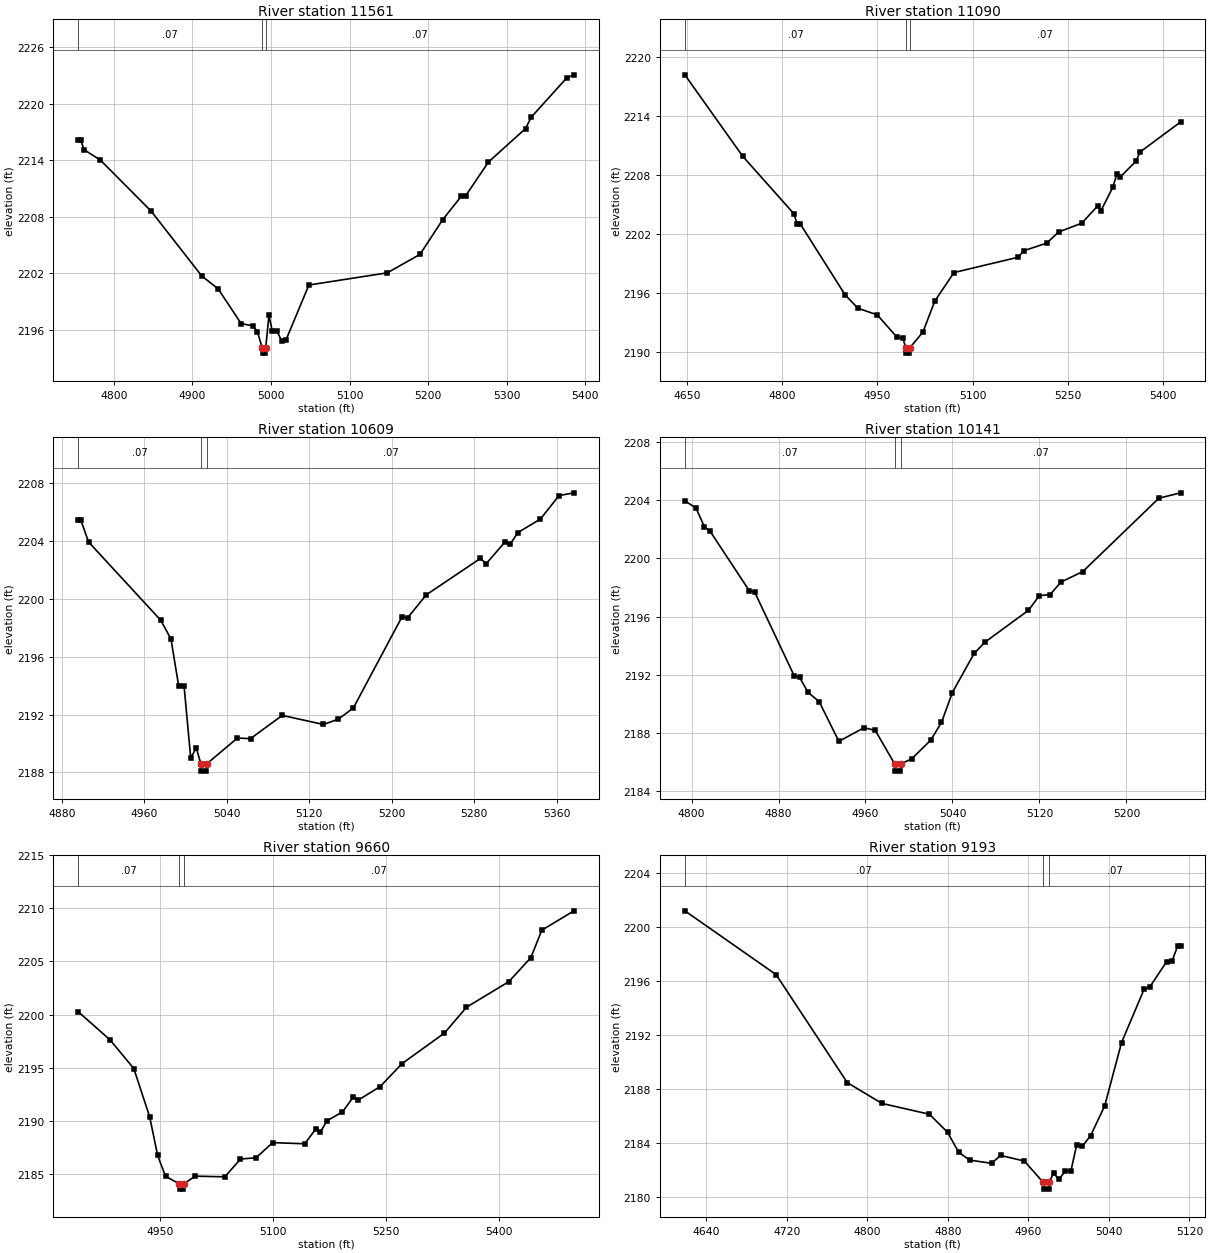
Type RM Length L Ch R = 1,11561,471,471,471
BEGIN DESCRIPTION:
Stream0233 25.0
END DESCRIPTION:
XS GIS Cut Line= 3
      1806625.03     13881925.02      1806825.00     13882075.00
      1807175.04     13882225.02
#Sta/Elev= 30
  4754.8 2216.19  4757.9 2216.19  4762.1 2215.12  4782.9 2214.02  4847.5 2208.61
  4912.1 2201.72  4932.9 2200.36  4962.1 2196.68  4976.6 2196.45  4982.9 2195.80
  4989.1 2194.05  4989.4 2193.55  4993.0 2193.55  4993.3 2194.05  4997.5 2197.55
  5001.6 2195.92  5007.5 2195.92  5013.8 2194.82  5019.3 2194.97  5048.3 2200.77
  5148.0 2202.06  5189.7 2204.02  5218.7 2207.71  5242.3 2210.19  5247.7 2210.22
  5276.8 2213.81  5323.9 2217.35  5331.2 2218.56  5376.5 2222.74  5385.6 2223.05
#Mann=3,-1,0
  4754.8    0.07       0  4989.1    0.05       0  4993.3    0.07       0
Bank Sta=4989.1,4993.3
Exp/Cntr=0.3,0.1

Type RM Length L Ch R = 1,11090,481,481,481
BEGIN DESCRIPTION:
Stream0233 24.0
END DESCRIPTION:
XS GIS Cut Line= 3
      1806275.02     13882525.00      1806625.00     13882475.00
      1807024.97     13882624.99
#Sta/Elev= 30
  4646.8 2218.15  4737.7 2209.89  4818.5 2204.03  4823.6 2203.02  4828.6 2202.99
  4899.3 2195.77  4919.5 2194.42  4949.8 2193.75  4980.1 2191.53  4990.2 2191.36
  4995.0 2190.36  4995.5 2189.86  5000.2 2189.86  5000.6 2190.36  5021.7 2192.00
  5040.4 2195.15  5070.6 2198.05  5171.2 2199.60  5181.0 2200.28  5216.6 2201.04
  5235.3 2202.17  5271.8 2203.07  5296.7 2204.81  5302.0 2204.33  5320.7 2206.72
  5327.0 2208.03  5332.3 2207.75  5357.2 2209.37  5363.5 2210.30  5427.5 2213.36
#Mann=3,-1,0
  4646.8    0.07       0  4995.0    0.05       0  5000.6    0.07       0
Bank Sta=4995,5000.6
Exp/Cntr=0.3,0.1

Type RM Length L Ch R = 1,10609,468,468,468
BEGIN DESCRIPTION:
Stream0233 23.0
END DESCRIPTION:
XS GIS Cut Line= 3
      1806424.99     13882925.00      1806525.00     13882925.00
      1806875.00     13882775.00
#Sta/Elev= 30
  4895.9 2205.48  4898.4 2205.48  4905.9 2203.95  4975.9 2198.53  4985.9 2197.22
  4993.4 2193.94  4998.6 2193.94  5005.0 2189.00  5010.4 2189.68  5014.9 2188.58
  5015.3 2188.08  5020.0 2188.08  5020.5 2188.58  5050.3 2190.37  5063.0 2190.33
  5093.8 2191.94  5133.7 2191.31  5148.2 2191.68  5162.7 2192.45  5209.9 2198.76
  5215.3 2198.69  5233.5 2200.29  5286.0 2202.81  5291.5 2202.44  5309.6 2203.93
  5315.0 2203.81  5322.3 2204.60  5344.1 2205.53  5362.2 2207.16  5376.7 2207.35
#Mann=3,-1,0
  4895.9    0.07       0  5014.9    0.05       0  5020.5    0.07       0
Bank Sta=5014.9,5020.5
Exp/Cntr=0.3,0.1

Type RM Length L Ch R = 1,10141,481,481,481
BEGIN DESCRIPTION:
Stream0233 22.0
END DESCRIPTION:
XS GIS Cut Line= 3
      1806375.05     13883325.01      1806575.00     13883375.00
      1806824.99     13883375.00
#Sta/Elev= 30
  4793.8 2203.97  4804.1 2203.47  4811.8 2202.18  4816.9 2201.89  4853.0 2197.79
  4858.2 2197.66  4894.3 2191.94  4899.4 2191.81  4907.1 2190.79  4917.4 2190.14
  4935.5 2187.41  4958.7 2188.35  4969.0 2188.16  4986.8 2185.86  4987.2 2185.36
  4992.0 2185.36  4992.5 2185.86  5002.4 2186.20  5019.9 2187.48  5029.9 2188.71
  5039.9 2190.77  5059.9 2193.46  5069.9 2194.24  5109.9 2196.43  5119.9 2197.44
  5129.9 2197.52  5139.9 2198.38  5159.9 2199.10  5229.9 2204.15  5249.9 2204.52
#Mann=3,-1,0
  4793.8    0.07       0  4986.8    0.05       0  4992.5    0.07       0
Bank Sta=4986.8,4992.5
Exp/Cntr=0.3,0.1

Type RM Length L Ch R = 1,9660,467,467,467
BEGIN DESCRIPTION:
Stream0233 21.0
END DESCRIPTION:
XS GIS Cut Line= 3
      1806325.01     13883775.00      1806475.00     13883825.00
      1806875.00     13884125.00
#Sta/Elev= 30
  4841.9 2200.27  4884.1 2197.62  4915.7 2194.92  4936.8 2190.36  4947.3 2186.74
  4957.8 2184.77  4976.0 2184.06  4976.5 2183.56  4981.4 2183.56  4981.9 2184.06
  4997.4 2184.78  5036.5 2184.72  5057.3 2186.39  5078.1 2186.52  5100.0 2187.94
  5142.7 2187.83  5157.3 2189.24  5163.5 2188.93  5171.9 2189.99  5192.7 2190.83
  5207.3 2192.26  5213.5 2191.94  5242.7 2193.22  5271.9 2195.39  5328.1 2198.26
  5357.3 2200.69  5413.5 2203.10  5442.7 2205.36  5457.3 2207.95  5500.0 2209.77
#Mann=3,-1,0
  4841.9    0.07       0  4976.0    0.05       0  4981.9    0.07       0
Bank Sta=4976,4981.9
Exp/Cntr=0.3,0.1

Type RM Length L Ch R = 1,9193,450,450,450
BEGIN DESCRIPTION:
Stream0233 20.0
END DESCRIPTION:
XS GIS Cut Line= 3
      1806174.98     13884124.99      1806525.00     13884275.00
      1806624.99     13884324.99
#Sta/Elev= 30
  4618.7 2201.19  4709.4 2196.47  4780.1 2188.48  4814.6 2186.94  4861.7 2186.14
  4879.8 2184.80  4890.7 2183.33  4901.6 2182.75  4923.4 2182.51  4932.4 2183.09
  4956.0 2182.68  4974.8 2181.10  4975.3 2180.60  4980.2 2180.60  4980.7 2181.10
  4985.0 2181.79  4990.4 2181.32  4996.8 2181.95  5002.3 2181.95  5007.9 2183.83
  5013.5 2183.76  5021.9 2184.56  5035.8 2186.75  5052.6 2191.44  5075.0 2195.39
  5080.6 2195.55  5097.3 2197.42  5102.9 2197.50  5108.5 2198.62  5111.3 2198.62
#Mann=3,-1,0
  4618.7    0.07       0  4974.8    0.05       0  4980.7    0.07       0
Bank Sta=4974.8,4980.7
Exp/Cntr=0.3,0.1

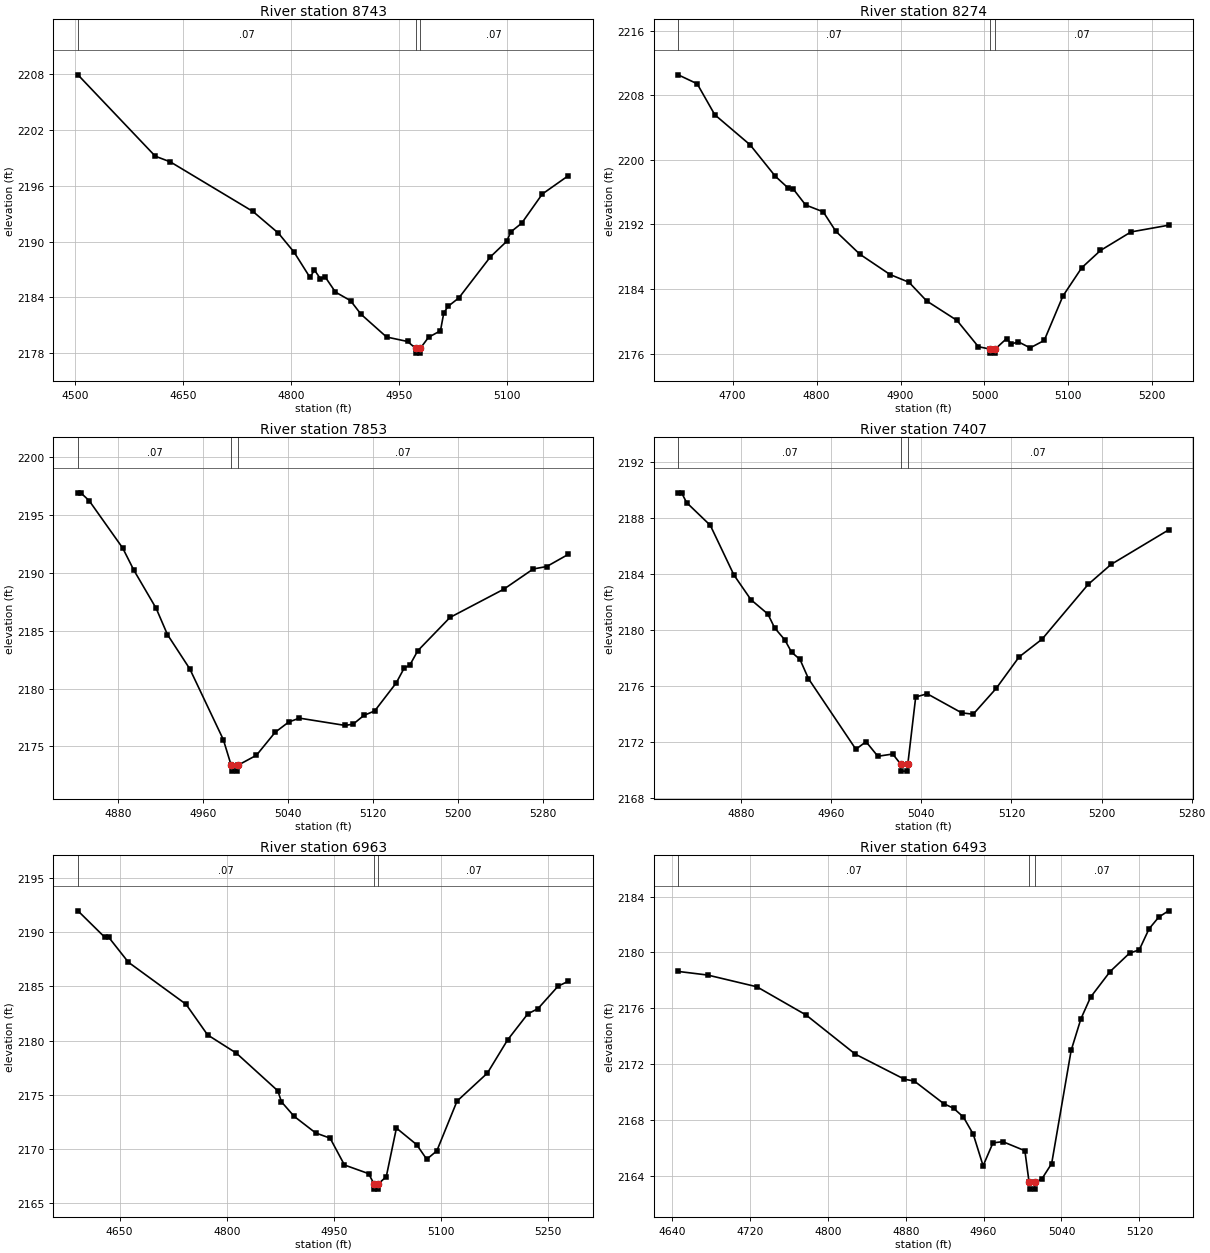
Type RM Length L Ch R = 1,8743,469,469,469
BEGIN DESCRIPTION:
Stream0233 19.0
END DESCRIPTION:
XS GIS Cut Line= 3
      1805974.96     13884374.97      1806375.00     13884675.00
      1806524.98     13884774.99
#Sta/Elev= 30
  4504.3 2207.89  4611.6 2199.16  4632.5 2198.55  4747.1 2193.23  4782.5 2190.90
  4804.3 2188.85  4826.2 2186.16  4832.5 2186.94  4840.8 2186.01  4847.1 2186.23
  4861.6 2184.58  4882.5 2183.66  4897.1 2182.20  4932.5 2179.76  4961.6 2179.28
  4973.2 2178.53  4973.7 2178.03  4978.7 2178.03  4979.2 2178.53  4990.8 2179.73
  5007.3 2180.43  5011.9 2182.34  5017.9 2183.05  5032.9 2183.96  5076.5 2188.35
  5099.0 2190.01  5105.0 2191.04  5120.0 2191.97  5148.6 2195.10  5184.6 2197.06
#Mann=3,-1,0
  4504.3    0.07       0  4973.2    0.05       0  4979.2    0.07       0
Bank Sta=4973.2,4979.2
Exp/Cntr=0.3,0.1

Type RM Length L Ch R = 1,8274,421,421,421
BEGIN DESCRIPTION:
Stream0233 18.0
END DESCRIPTION:
XS GIS Cut Line= 3
      1805774.97     13884824.98      1806075.00     13885025.00
      1806275.00     13885125.00
#Sta/Elev= 30
  4635.1 2210.54  4657.7 2209.43  4678.7 2205.59  4720.8 2201.86  4750.8 2197.97
  4765.8 2196.54  4771.8 2196.44  4786.9 2194.41  4807.9 2193.56  4822.9 2191.15
  4851.5 2188.31  4887.5 2185.79  4910.1 2184.83  4931.1 2182.52  4967.2 2180.11
  4992.7 2176.85  5006.6 2176.55  5007.1 2176.05  5012.3 2176.05  5012.8 2176.55
  5026.4 2177.86  5032.0 2177.18  5040.4 2177.45  5054.4 2176.70  5071.2 2177.62
  5093.5 2183.13  5115.9 2186.63  5138.2 2188.77  5174.6 2191.07  5219.3 2191.90
#Mann=3,-1,0
  4635.1    0.07       0  5006.6    0.05       0  5012.8    0.07       0
Bank Sta=5006.6,5012.8
Exp/Cntr=0.3,0.1

Type RM Length L Ch R = 1,7853,446,446,446
BEGIN DESCRIPTION:
Stream0233 17.0
END DESCRIPTION:
XS GIS Cut Line= 3
      1805724.96     13885324.99      1805875.00     13885375.00
      1806175.01     13885425.00
#Sta/Elev= 30
  4841.9 2196.91  4844.6 2196.91  4852.5 2196.23  4884.1 2192.14  4894.6 2190.23
  4915.7 2186.92  4926.3 2184.66  4947.4 2181.69  4979.0 2175.58  4986.4 2173.36
  4986.9 2172.86  4992.1 2172.86  4992.6 2173.36  5010.2 2174.23  5027.9 2176.22
  5040.6 2177.10  5050.7 2177.44  5093.8 2176.81  5101.4 2176.92  5111.6 2177.68
  5121.7 2178.06  5142.0 2180.48  5149.6 2181.78  5154.7 2182.00  5162.3 2183.26
  5192.7 2186.14  5243.4 2188.58  5271.2 2190.33  5283.9 2190.54  5304.2 2191.59
#Mann=3,-1,0
  4841.9    0.07       0  4986.4    0.05       0  4992.6    0.07       0
Bank Sta=4986.4,4992.6
Exp/Cntr=0.3,0.1

Type RM Length L Ch R = 1,7407,444,444,444
BEGIN DESCRIPTION:
Stream0233 16.0
END DESCRIPTION:
XS GIS Cut Line= 3
      1805575.04     13885675.03      1805725.00     13885775.00
      1805975.02     13885825.00
#Sta/Elev= 30
  4824.2 2189.77  4827.2 2189.77  4831.7 2189.07  4852.7 2187.45  4873.7 2183.90
  4888.8 2182.14  4903.8 2181.12  4909.8 2180.13  4918.8 2179.28  4924.8 2178.40
  4932.3 2177.88  4939.8 2176.51  4981.9 2171.47  4990.9 2172.01  5001.4 2170.97
  5014.6 2171.13  5021.7 2170.41  5022.2 2169.91  5027.5 2169.91  5028.0 2170.41
  5035.0 2175.20  5045.2 2175.43  5075.8 2174.07  5086.0 2173.97  5106.4 2175.81
  5126.8 2178.06  5147.2 2179.33  5188.0 2183.23  5208.4 2184.66  5259.4 2187.12
#Mann=3,-1,0
  4824.2    0.07       0  5021.7    0.05       0  5028.0    0.07       0
Bank Sta=5021.7,5028
Exp/Cntr=0.3,0.1

Type RM Length L Ch R = 1,6963,470,470,470
BEGIN DESCRIPTION:
Stream0233 15.0
END DESCRIPTION:
XS GIS Cut Line= 3
      1805425.00     13885724.97      1805475.00     13886125.00
      1805675.01     13886325.01
#Sta/Elev= 30
  4591.8 2191.99  4629.6 2189.53  4634.7 2189.56  4662.4 2187.24  4743.0 2183.36
  4773.2 2180.53  4813.5 2178.84  4871.5 2175.36  4876.5 2174.35  4894.2 2173.01
  4924.4 2171.47  4944.6 2170.99  4964.7 2168.51  4998.5 2167.71  5005.9 2166.78
  5006.4 2166.28  5011.8 2166.28  5012.3 2166.78  5023.2 2167.43  5037.4 2171.92
  5065.7 2170.39  5079.8 2169.04  5093.9 2169.81  5122.2 2174.41  5164.7 2177.00
  5192.9 2180.06  5221.2 2182.47  5235.4 2182.95  5263.6 2185.03  5277.8 2185.48
#Mann=3,-1,0
  4591.8    0.07       0  5005.9    0.05       0  5012.3    0.07       0
Bank Sta=5005.9,5012.3
Exp/Cntr=0.3,0.1

Type RM Length L Ch R = 1,6493,462,462,462
BEGIN DESCRIPTION:
Stream0233 14.0
END DESCRIPTION:
XS GIS Cut Line= 3
      1805174.99     13886025.04      1805125.00     13886375.00
      1805125.00     13886524.99
#Sta/Elev= 30
  4646.4 2178.64  4676.7 2178.38  4727.2 2177.54  4777.7 2175.52  4828.2 2172.72
  4878.7 2170.92  4888.8 2170.79  4919.1 2169.17  4929.2 2168.84  4939.3 2168.21
  4949.4 2166.98  4959.5 2164.72  4969.6 2166.36  4979.7 2166.45  5002.4 2165.80
  5006.7 2163.55  5007.2 2163.05  5012.7 2163.05  5013.2 2163.55  5019.9 2163.79
  5029.9 2164.88  5049.9 2172.98  5059.9 2175.24  5069.9 2176.80  5089.9 2178.63
  5109.9 2179.95  5119.9 2180.19  5129.9 2181.69  5139.9 2182.53  5149.9 2182.98
#Mann=3,-1,0
  4646.4    0.07       0  5006.7    0.05       0  5013.2    0.07       0
Bank Sta=5006.7,5013.2
Exp/Cntr=0.3,0.1

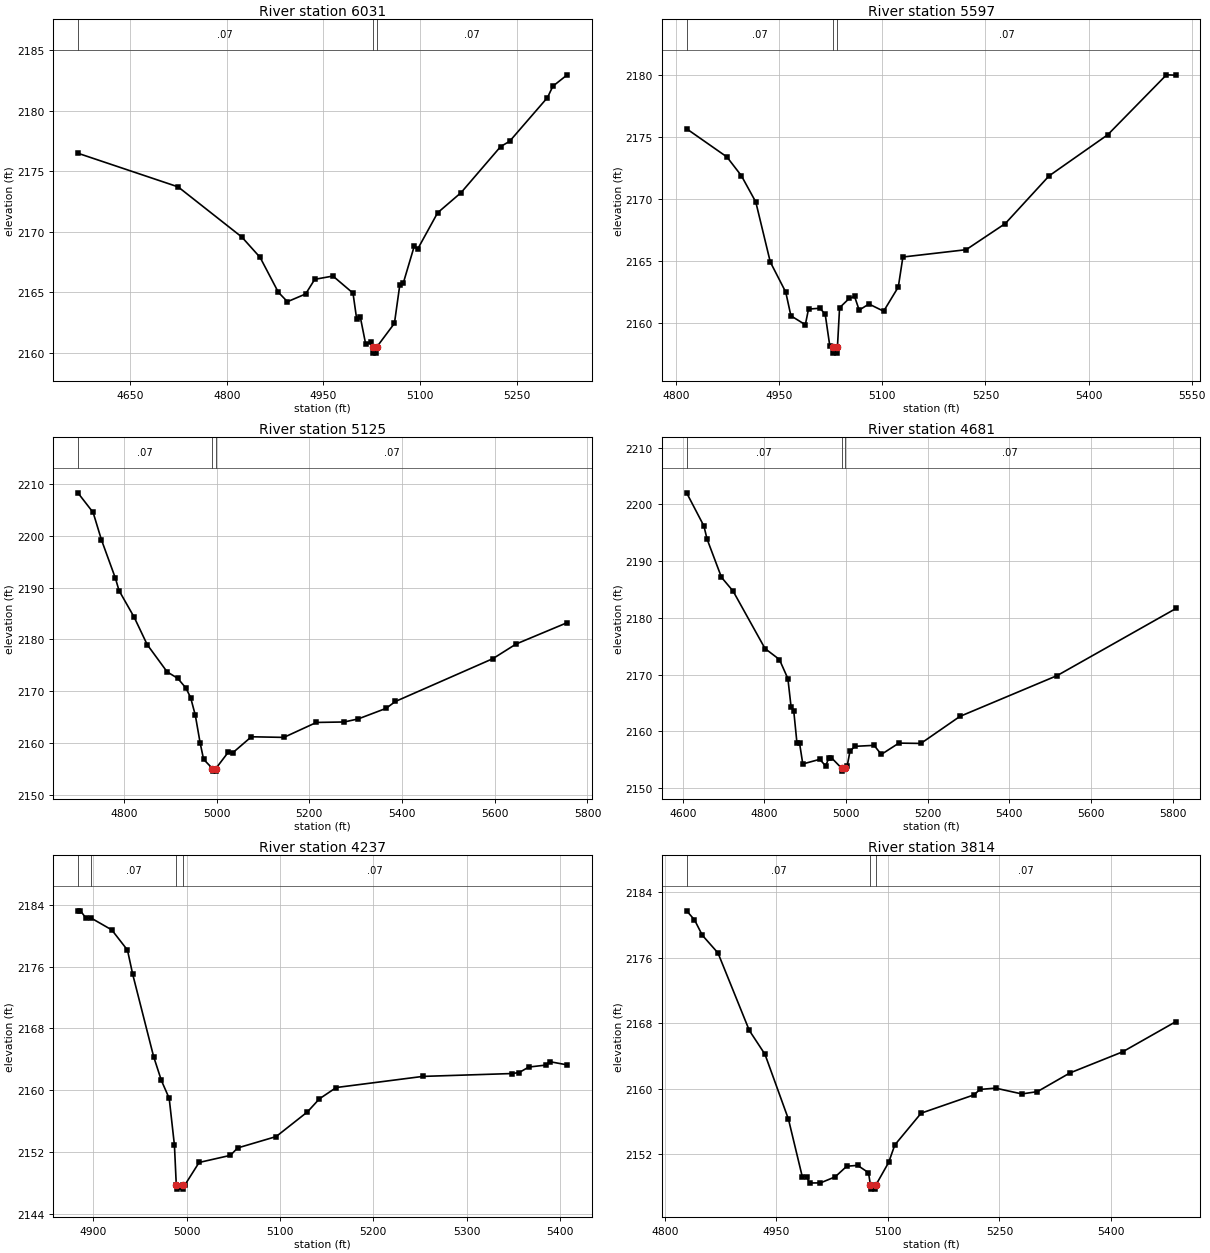
Type RM Length L Ch R = 1,6031,434,434,434
BEGIN DESCRIPTION:
Stream0233 13.0
END DESCRIPTION:
XS GIS Cut Line= 3
      1804975.03     13886024.97      1804675.00     13886325.00
      1804824.99     13886624.98
#Sta/Elev= 30
  4568.7 2176.49  4724.3 2173.71  4823.3 2169.56  4851.6 2167.88  4879.9 2165.00
  4894.0 2164.22  4922.3 2164.86  4936.4 2166.07  4964.7 2166.34  4995.8 2164.93
  5001.4 2162.83  5007.0 2162.99  5015.4 2160.74  5023.8 2160.87  5026.1 2160.47
  5026.6 2159.97  5032.1 2159.97  5032.6 2160.47  5060.1 2162.43  5068.5 2165.62
  5074.1 2165.80  5090.8 2168.79  5096.4 2168.59  5127.2 2171.57  5163.5 2173.23
  5225.0 2177.04  5239.0 2177.48  5297.7 2181.09  5306.1 2182.03  5328.4 2182.97
#Mann=3,-1,0
  4568.7    0.07       0  5026.1    0.05       0  5032.6    0.07       0
Bank Sta=5026.1,5032.6
Exp/Cntr=0.3,0.1

Type RM Length L Ch R = 1,5597,472,472,472
BEGIN DESCRIPTION:
Stream0233 12.0
END DESCRIPTION:
XS GIS Cut Line= 3
      1804125.01     13886225.01      1804275.00     13886325.00
      1804675.02     13886675.02
#Sta/Elev= 30
  4815.4 2175.69  4874.0 2173.42  4895.0 2171.91  4916.0 2169.79  4937.1 2164.95
  4959.6 2162.52  4967.1 2160.61  4988.1 2159.89  4992.7 2161.15  5009.4 2161.22
  5017.0 2160.73  5023.7 2158.17  5027.7 2158.10  5028.2 2157.60  5034.3 2157.60
  5034.8 2158.10  5037.9 2161.26  5052.1 2162.02  5059.7 2162.17  5066.4 2161.07
  5080.6 2161.56  5102.0 2160.98  5123.3 2162.93  5130.0 2165.35  5222.0 2165.94
  5279.0 2168.05  5342.6 2171.89  5428.0 2175.21  5513.4 2180.04  5527.2 2180.01
#Mann=3,-1,0
  4815.4    0.07       0  5027.7    0.05       0  5034.8    0.07       0
Bank Sta=5027.7,5034.8
Exp/Cntr=0.3,0.1

Type RM Length L Ch R = 1,5125,444,444,444
BEGIN DESCRIPTION:
Stream0233 11.0
END DESCRIPTION:
XS GIS Cut Line= 3
      1803675.01     13886625.00      1803975.00     13886675.00
      1804725.01     13886725.00
#Sta/Elev= 30
  4700.6 2208.33  4733.5 2204.53  4751.3 2199.28  4781.7 2191.79  4789.3 2189.45
  4822.2 2184.26  4850.1 2179.00  4893.2 2173.72  4916.0 2172.48  4933.8 2170.59
  4943.9 2168.74  4954.0 2165.32  4964.2 2160.07  4971.8 2156.82  4991.0 2155.04
  4991.5 2154.54  4997.7 2154.54  4998.2 2155.04  5024.8 2158.17  5034.8 2158.09
  5074.9 2161.18  5145.0 2161.06  5215.2 2163.95  5275.3 2164.04  5305.4 2164.63
  5365.5 2166.67  5385.6 2168.00  5596.0 2176.28  5646.1 2179.11  5756.4 2183.24
#Mann=3,-1,0
  4700.6    0.07       0  4991.0    0.05       0  4998.2    0.07       0
Bank Sta=4991,4998.2
Exp/Cntr=0.3,0.1

Type RM Length L Ch R = 1,4681,444,444,444
BEGIN DESCRIPTION:
Stream0233 10.0
END DESCRIPTION:
XS GIS Cut Line= 3
      1803624.98     13886824.98      1803925.00     13887075.00
      1804674.98     13886775.01
#Sta/Elev= 30
  4609.5 2202.02  4651.8 2196.18  4659.6 2193.87  4694.8 2187.14  4723.4 2184.69
  4801.5 2174.58  4836.7 2172.65  4857.5 2169.28  4865.3 2164.30  4871.8 2163.62
  4879.6 2158.01  4886.1 2157.90  4894.0 2154.24  4935.6 2155.06  4949.9 2153.90
  4957.7 2155.27  4964.2 2155.33  4989.3 2153.48  4989.8 2152.98  4996.5 2153.48
  5002.7 2153.88  5009.5 2156.48  5021.6 2157.35  5068.7 2157.52  5086.2 2155.92
  5129.3 2157.92  5183.1 2157.86  5278.7 2162.62  5517.0 2169.82  5807.8 2181.64
#Mann=3,-1,0
  4609.5    0.07       0  4989.3    0.05       0  4996.5    0.07       0
Bank Sta=4989.3,4996.5
Exp/Cntr=0.3,0.1

Type RM Length L Ch R = 1,4237,423,423,423
BEGIN DESCRIPTION:
Stream0233 9.0
END DESCRIPTION:
XS GIS Cut Line= 3
      1804075.00     13887525.00      1804125.00     13887425.00
      1804225.00     13887025.01
#Sta/Elev= 30
  4883.6 2183.22  4886.4 2183.22  4892.0 2182.31  4897.7 2182.29  4919.9 2180.75
  4936.7 2178.14  4942.3 2175.01  4964.7 2164.36  4973.0 2161.27  4981.4 2158.95
  4987.0 2152.88  4989.0 2147.70  4989.5 2147.20  4995.7 2147.20  4996.2 2147.70
  4998.0 2147.70  5013.4 2150.65  5046.9 2151.57  5054.7 2152.53  5095.9 2154.00
  5129.4 2157.19  5142.3 2158.89  5160.3 2160.35  5253.1 2161.79  5348.4 2162.16
  5356.2 2162.29  5366.5 2163.00  5384.5 2163.25  5389.7 2163.68  5407.7 2163.28
#Mann=4,-1,0
  4883.6     0.1       0  4897.7    0.07       0  4989.0    0.05       0
  4996.2    0.07       0
Bank Sta=4989,4996.2
Exp/Cntr=0.3,0.1

Type RM Length L Ch R = 1,3814,457,457,457
BEGIN DESCRIPTION:
Stream0233 8.0
END DESCRIPTION:
XS GIS Cut Line= 3
      1804425.00     13887775.01      1804475.00     13887625.00
      1804774.98     13887225.02
#Sta/Elev= 30
  4829.3 2181.72  4839.9 2180.62  4850.4 2178.74  4871.5 2176.57  4913.6 2167.11
  4934.7 2164.19  4966.3 2156.25  4984.8 2149.26  4990.6 2149.26  4994.7 2148.47
  5009.3 2148.48  5029.1 2149.22  5044.7 2150.52  5059.3 2150.62  5073.9 2149.73
  5076.5 2148.22  5077.0 2147.72  5083.3 2147.72  5083.8 2148.22  5101.0 2150.98
  5109.3 2153.12  5144.7 2157.00  5215.6 2159.23  5223.9 2159.90  5244.7 2160.06
  5280.1 2159.35  5301.0 2159.63  5344.7 2161.91  5415.6 2164.49  5487.4 2168.19
#Mann=3,-1,0
  4829.3    0.07       0  5076.5    0.05       0  5083.8    0.07       0
Bank Sta=5076.5,5083.8
Exp/Cntr=0.3,0.1

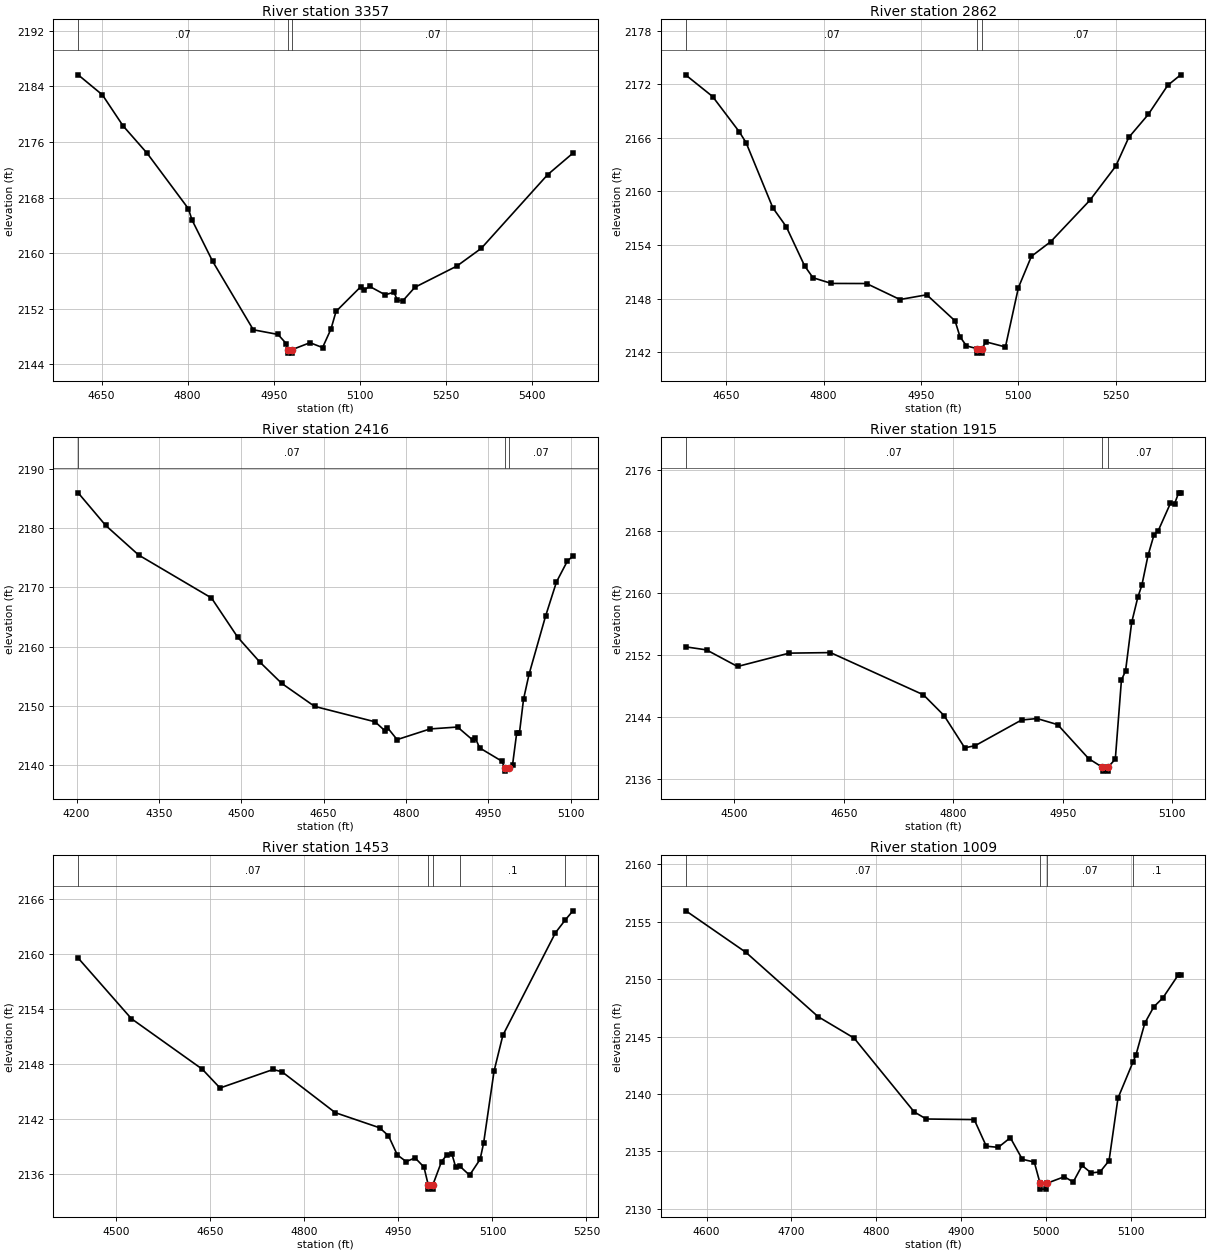
Type RM Length L Ch R = 1,3357,495,495,495
BEGIN DESCRIPTION:
Stream0233 7.0
END DESCRIPTION:
XS GIS Cut Line= 3
      1804575.03     13887974.98      1804875.00     13887725.00
      1805125.01     13887324.98
#Sta/Elev= 30
  4609.3 2185.66  4651.6 2182.77  4687.4 2178.33  4729.7 2174.35  4801.3 2166.40
  4807.8 2164.75  4843.6 2158.82  4914.5 2148.96  4957.5 2148.29  4971.8 2146.98
  4974.6 2146.10  4975.1 2145.60  4981.4 2145.60  4981.9 2146.10  5013.3 2147.10
  5035.2 2146.40  5049.9 2149.08  5058.7 2151.61  5101.8 2155.16  5107.7 2154.68
  5117.1 2155.21  5144.2 2154.00  5159.6 2154.36  5165.5 2153.24  5174.9 2153.12
  5196.1 2155.08  5269.2 2158.13  5311.7 2160.68  5427.3 2171.28  5471.5 2174.39
#Mann=3,-1,0
  4609.3    0.07       0  4974.6    0.05       0  4981.9    0.07       0
Bank Sta=4974.6,4981.9
Exp/Cntr=0.3,0.1

Type RM Length L Ch R = 1,2862,446,446,446
BEGIN DESCRIPTION:
Stream0233 6.0
END DESCRIPTION:
XS GIS Cut Line= 3
      1804825.02     13888175.00      1805225.00     13888075.00
      1805575.01     13888075.00
#Sta/Elev= 30
  4587.7 2173.01  4628.9 2170.61  4670.1 2166.65  4680.5 2165.44  4721.7 2158.15
  4742.3 2156.05  4770.6 2151.66  4783.5 2150.33  4811.9 2149.69  4866.0 2149.68
  4917.5 2147.89  4958.8 2148.42  5002.5 2145.49  5010.0 2143.72  5020.0 2142.70
  5036.3 2142.39  5036.8 2141.89  5043.2 2141.89  5043.7 2142.39  5050.0 2143.15
  5080.0 2142.58  5100.0 2149.22  5120.0 2152.72  5150.0 2154.38  5210.0 2158.99
  5250.0 2162.82  5270.0 2166.03  5300.0 2168.60  5330.0 2171.86  5350.0 2173.04
#Mann=3,-1,0
  4587.7    0.07       0  5036.3    0.05       0  5043.7    0.07       0
Bank Sta=5036.3,5043.7
Exp/Cntr=0.3,0.1

Type RM Length L Ch R = 1,2416,501,501,501
BEGIN DESCRIPTION:
Stream0233 5.0
END DESCRIPTION:
XS GIS Cut Line= 3
      1804675.05     13888375.00      1805475.00     13888425.00
      1805574.98     13888425.00
#Sta/Elev= 30
  4202.9 2185.95  4253.0 2180.46  4313.1 2175.47  4445.8 2168.23  4493.4 2161.64
  4533.5 2157.47  4573.6 2153.85  4633.7 2149.96  4743.9 2147.36  4761.4 2145.89
  4766.5 2146.37  4784.0 2144.36  4844.1 2146.16  4894.2 2146.48  4921.8 2144.29
  4926.8 2144.58  4934.3 2142.97  4974.4 2140.75  4980.6 2139.55  4981.1 2139.05
  4988.1 2139.55  4994.4 2140.14  5001.9 2145.48  5006.9 2145.48  5014.4 2151.19
  5024.4 2155.37  5054.4 2165.14  5074.4 2170.94  5094.4 2174.48  5104.4 2175.28
#Mann=3,-1,0
  4202.9    0.07       0  4980.6    0.05       0  4988.1    0.07       0
Bank Sta=4980.6,4988.1
Exp/Cntr=0.3,0.1

Type RM Length L Ch R = 1,1915,462,462,462
BEGIN DESCRIPTION:
Stream0233 4.0
END DESCRIPTION:
XS GIS Cut Line= 3
      1805075.01     13888525.01      1805475.00     13888925.00
      1805575.02     13888975.01
#Sta/Elev= 30
  4433.9 2153.05  4462.2 2152.66  4504.6 2150.51  4575.3 2152.24  4631.9 2152.31
  4759.2 2146.84  4787.4 2144.16  4815.7 2139.98  4829.9 2140.25  4893.5 2143.58
  4914.7 2143.77  4943.0 2142.98  4985.4 2138.58  5004.2 2137.46  5004.7 2136.96
  5011.3 2136.96  5011.8 2137.46  5021.9 2138.51  5030.3 2148.77  5035.9 2149.92
  5044.3 2156.21  5052.7 2159.47  5058.3 2161.05  5066.7 2164.90  5075.0 2167.60
  5080.6 2168.08  5097.4 2171.65  5103.0 2171.57  5108.6 2173.00  5111.4 2173.00
#Mann=3,-1,0
  4433.9    0.07       0  5004.2    0.05       0  5011.8    0.07       0
Bank Sta=5004.2,5011.8
Exp/Cntr=0.3,0.1

Type RM Length L Ch R = 1,1453,444,444,444
BEGIN DESCRIPTION:
Stream0233 3.0
END DESCRIPTION:
XS GIS Cut Line= 3
      1804824.99     13888874.99      1805225.00     13889275.00
      1805424.99     13889375.00
#Sta/Elev= 30
  4439.1 2159.58  4524.0 2152.97  4637.1 2147.46  4665.4 2145.41  4750.2 2147.43
  4764.4 2147.17  4849.2 2142.72  4920.0 2141.07  4934.1 2140.20  4948.2 2138.11
  4962.4 2137.38  4976.5 2137.79  4990.7 2136.79  4997.4 2134.88  4997.9 2134.38
  5004.6 2134.38  5005.1 2134.88  5018.8 2137.39  5027.2 2138.11  5035.5 2138.18
  5041.1 2136.83  5047.5 2136.91  5063.5 2135.90  5080.3 2137.63  5085.9 2139.41
  5102.6 2147.27  5116.6 2151.16  5200.5 2162.34  5216.4 2163.76  5228.4 2164.73
#Mann=5,-1,0
  4439.1    0.07       0  4997.4    0.05       0  5005.1    0.07       0
  5047.5     0.1       0  5216.4    0.07       0
Bank Sta=4997.4,5005.1
Exp/Cntr=0.3,0.1

Type RM Length L Ch R = 1,1009,472,472,472
BEGIN DESCRIPTION:
Stream0233 2.0
END DESCRIPTION:
XS GIS Cut Line= 3
      1804624.99     13889274.99      1804925.00     13889575.00
      1805075.01     13889625.00
#Sta/Elev= 30
  4575.7 2155.96  4646.4 2152.34  4731.3 2146.74  4773.7 2144.87  4844.4 2138.44
  4858.6 2137.82  4915.1 2137.77  4929.3 2135.45  4943.4 2135.35  4957.6 2136.19
  4971.7 2134.31  4985.8 2134.07  4992.6 2132.21  4993.1 2131.71  4999.8 2131.71
  5000.3 2132.21  5021.1 2132.79  5031.6 2132.33  5042.1 2133.77  5052.7 2133.12
  5063.2 2133.21  5073.8 2134.19  5084.3 2139.64  5102.0 2142.79  5105.4 2143.39
  5115.9 2146.18  5126.5 2147.60  5137.0 2148.36  5155.5 2150.40  5158.1 2150.40
#Mann=4,-1,0
  4575.7    0.07       0  4992.6    0.05       0  5000.3    0.07       0
  5102.0     0.1       0
Bank Sta=4992.6,5000.3
Exp/Cntr=0.3,0.1

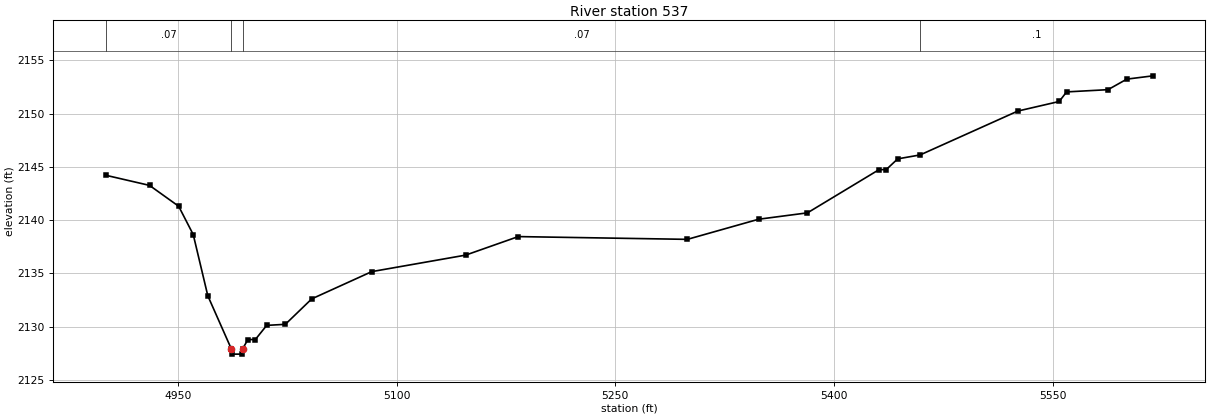
Type RM Length L Ch R = 1,537,0,0,0
BEGIN DESCRIPTION:
Stream0233 1.0
END DESCRIPTION:
XS GIS Cut Line= 3
      1804524.96     13889925.00      1804625.00     13889925.00
      1805224.99     13889775.00
#Sta/Elev= 30
  4900.4 2144.21  4930.4 2143.26  4950.4 2141.30  4960.4 2138.64  4970.4 2132.89
  4986.5 2127.91  4987.0 2127.41  4993.8 2127.41  4994.3 2127.91  4997.9 2128.78
  5003.0 2128.78  5010.8 2130.11  5023.6 2130.21  5041.7 2132.60  5082.9 2135.16
  5147.3 2136.71  5183.4 2138.45  5299.4 2138.19  5348.3 2140.08  5381.8 2140.68
  5430.8 2144.73  5435.9 2144.75  5443.7 2145.75  5459.1 2146.12  5526.1 2150.24
  5554.5 2151.14  5559.6 2152.04  5588.0 2152.25  5600.9 2153.24  5618.9 2153.55
#Mann=4,-1,0
  4900.4    0.07       0  4986.5    0.05       0  4994.3    0.07       0
  5459.1     0.1       0
Bank Sta=4986.5,4994.3
Exp/Cntr=0.3,0.1

Chan Stop Cuts=-1