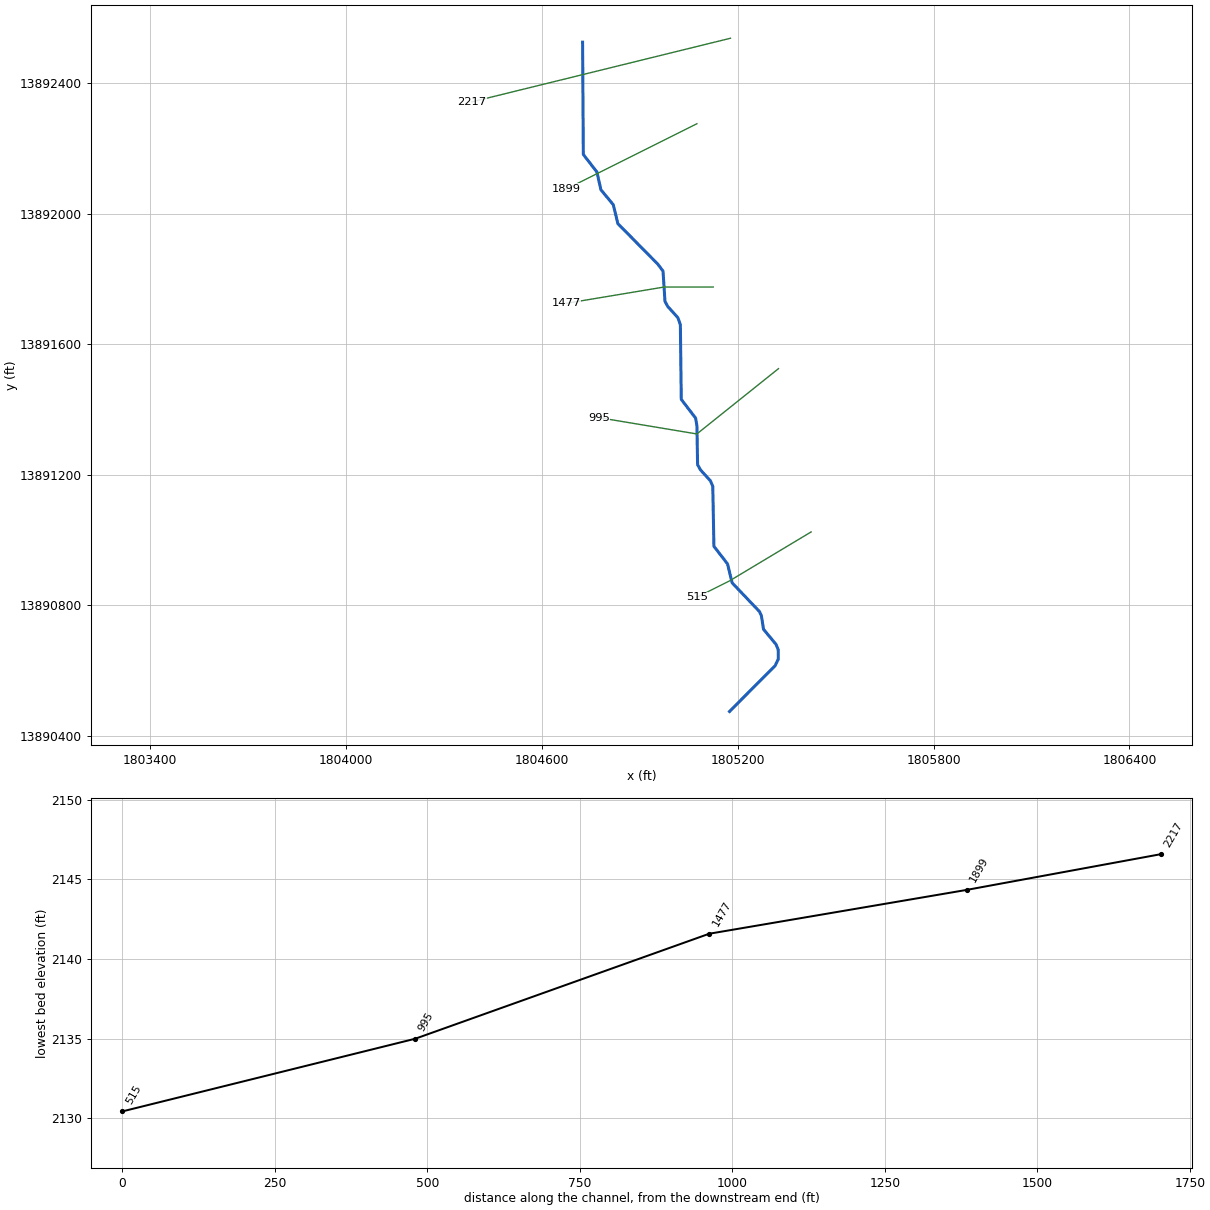
--- Stream0234.prj (project) ---

Proj Title=Stream0234 Base Level Engineering
Current Plan=p01
Default Exp/Contr=0.3,0.1
English Units
Geom File=g01
Flow File=f01
Plan File=p01
BEGIN DESCRIPTION:
Stream0234
END DESCRIPTION:

--- Stream0234.p01 (plan) ---

Plan Title=Multiple Run
Short Identifier=Multiple
Geom File=g01
Flow File=f01
Subcritical Flow
K Sum by GR= 0
Std Step Tol= 0.01
Critical Tol= 0.01
Num of Std Step Trials= 20
Max Error Tol= 0.3
Flow Tol Ratio= 0.001
Split Flow NTrial= 30
Split Flow Tol= 0.02
Split Flow Ratio= 0.02
Log Output Level= 0
Friction Slope Method= 1
Unsteady Friction Slope Method= 2
Unsteady Bridges Friction Slope Method= 1
Parabolic Critical Depth
Global Vel Dist=  1 , 1 , 1
Global Log Level= 0
CheckData=True
Encroach Param= -1, 0, 0, 0
BEGIN DESCRIPTION:
Multiple Run
END DESCRIPTION:

--- Stream0234.f01 (steady flow) ---

Flow Title=Multiple
Number of Profiles=7
Profile Names=10-year,25-year,50-year,1pct_min,100-year,1pct_plu,500-year
River Rch & RM= Stream0234,Reach-1,2217
     821    1379    1903    1270    2535    5058    4443
Boundary for River Rch & Prof#=Stream0234,Reach-1,1
Up Type=0
Dn Type=3
Dn Slope=0.005
Boundary for River Rch & Prof#=Stream0234,Reach-1,2
Up Type=0
Dn Type=3
Dn Slope=0.005
Boundary for River Rch & Prof#=Stream0234,Reach-1,3
Up Type=0
Dn Type=3
Dn Slope=0.005
Boundary for River Rch & Prof#=Stream0234,Reach-1,4
Up Type=0
Dn Type=3
Dn Slope=0.005
Boundary for River Rch & Prof#=Stream0234,Reach-1,5
Up Type=0
Dn Type=3
Dn Slope=0.005
Boundary for River Rch & Prof#=Stream0234,Reach-1,6
Up Type=0
Dn Type=3
Dn Slope=0.005
Boundary for River Rch & Prof#=Stream0234,Reach-1,7
Up Type=0
Dn Type=3
Dn Slope=0.005

--- Stream0234.g01 (geometry) ---

Geom Title=Existing Conditions

River Reach=Stream0234,Reach-1
Reach XY= 30
      1804725.00     13892525.00      1804727.24     13892180.93
      1804768.88     13892127.18      1804781.08     13892072.80
      1804818.90     13892027.19      1804833.14     13891968.94
      1804955.37     13891845.15      1804971.39     13891823.50
      1804977.36     13891730.98      1804985.90     13891715.37
      1805016.86     13891681.06      1805024.48     13891659.78
      1805027.26     13891430.94      1805071.21     13891373.43
      1805075.18     13891350.07      1805077.27     13891230.94
      1805085.86     13891215.36      1805116.86     13891181.06
      1805123.78     13891164.49      1805127.24     13890980.93
      1805168.86     13890927.17      1805183.16     13890868.95
      1805266.85     13890781.05      1805272.50     13890768.96
      1805279.25     13890726.73      1805317.26     13890680.93
      1805324.30     13890664.30      1805324.41     13890635.62
      1805314.82     13890615.31      1805175.00     13890475.00

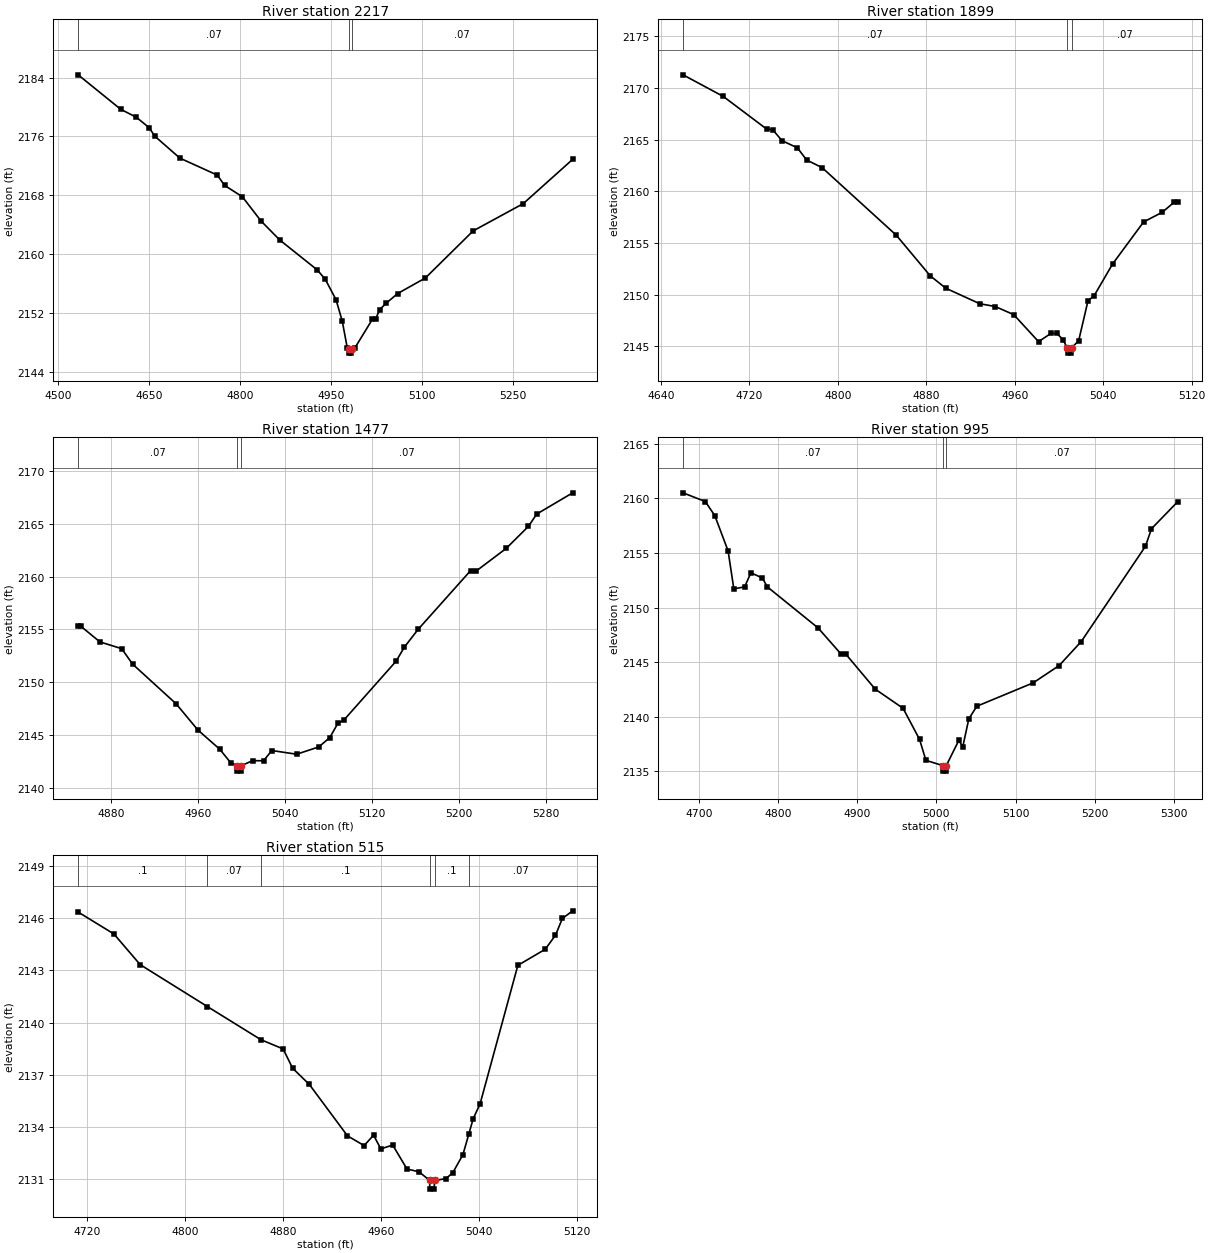
Type RM Length L Ch R = 1,2217,318,318,318
BEGIN DESCRIPTION:
Stream0234 5.0
END DESCRIPTION:
XS GIS Cut Line= 2
      1805177.98     13892536.82      1804385.90     13892341.96
#Sta/Elev= 30
  4533.5 2184.37  4603.7 2179.69  4629.3 2178.62  4650.4 2177.21  4660.1 2176.03
  4701.3 2173.06  4763.1 2170.75  4775.0 2169.36  4804.3 2167.82  4835.2 2164.52
  4866.1 2161.94  4927.9 2157.88  4941.1 2156.61  4958.8 2153.85  4969.1 2150.95
  4977.4 2147.31  4980.6 2147.08  4980.8 2146.58  4984.3 2146.58  4984.6 2147.08
  4989.7 2147.25  5019.0 2151.19  5024.1 2151.20  5030.9 2152.49  5041.2 2153.33
  5060.5 2154.67  5106.2 2156.78  5185.1 2163.18  5267.7 2166.88  5349.2 2172.89
#Mann=3,-1,0
  4533.5    0.07       0  4980.6    0.05       0  4984.6    0.07       0
Bank Sta=4980.6,4984.6
Exp/Cntr=0.3,0.1

Type RM Length L Ch R = 1,1899,422,422,422
BEGIN DESCRIPTION:
Stream0234 4.0
END DESCRIPTION:
XS GIS Cut Line= 3
      1805075.02     13892275.01      1804775.00     13892125.00
      1804675.03     13892075.01
#Sta/Elev= 30
  4660.0 2171.26  4696.4 2169.17  4735.5 2166.02  4741.1 2165.95  4749.5 2164.89
  4763.4 2164.20  4771.8 2163.02  4785.8 2162.28  4852.9 2155.74  4883.6 2151.81
  4897.6 2150.62  4928.3 2149.12  4942.3 2148.85  4959.1 2148.06  4981.5 2145.45
  4992.6 2146.24  4998.2 2146.24  5003.8 2145.61  5007.4 2144.84  5007.7 2144.34
  5011.2 2144.34  5011.4 2144.84  5017.8 2145.55  5026.2 2149.40  5031.8 2149.90
  5048.5 2152.97  5076.5 2157.03  5093.3 2157.96  5104.4 2158.96  5107.2 2158.96
#Mann=3,-1,0
  4660.0    0.07       0  5007.4    0.05       0  5011.4    0.07       0
Bank Sta=5007.4,5011.4
Exp/Cntr=0.3,0.1

Type RM Length L Ch R = 1,1477,482,482,482
BEGIN DESCRIPTION:
Stream0234 3.0
END DESCRIPTION:
XS GIS Cut Line= 3
      1805125.04     13891775.00      1804975.00     13891775.00
      1804674.98     13891725.00
#Sta/Elev= 30
  4850.0 2155.30  4852.5 2155.30  4870.0 2153.82  4890.0 2153.18  4900.0 2151.72
  4940.0 2147.96  4960.0 2145.48  4980.0 2143.67  4990.0 2142.40  4995.5 2142.09
  4995.8 2141.59  4999.3 2141.59  4999.5 2142.09  5010.2 2142.58  5020.3 2142.57
  5027.9 2143.54  5050.7 2143.19  5071.0 2143.88  5081.1 2144.76  5088.7 2146.14
  5093.8 2146.39  5142.0 2151.99  5149.6 2153.32  5162.2 2155.00  5210.4 2160.56
  5215.5 2160.52  5243.3 2162.68  5263.6 2164.76  5271.2 2165.92  5304.2 2167.93
#Mann=3,-1,0
  4850.0    0.07       0  4995.5    0.05       0  4999.5    0.07       0
Bank Sta=4995.5,4999.5
Exp/Cntr=0.3,0.1

Type RM Length L Ch R = 1,995,480,480,480
BEGIN DESCRIPTION:
Stream0234 2.0
END DESCRIPTION:
XS GIS Cut Line= 3
      1805325.04     13891525.03      1805075.00     13891325.00
      1804775.04     13891374.99
#Sta/Elev= 30
  4680.2 2160.52  4708.3 2159.72  4720.3 2158.43  4737.1 2155.19  4744.3 2151.72
  4757.9 2151.89  4765.9 2153.19  4780.3 2152.71  4786.7 2151.89  4850.7 2148.13
  4879.5 2145.75  4885.9 2145.71  4922.8 2142.52  4958.0 2140.76  4978.8 2137.91
  4986.8 2135.99  5008.5 2135.50  5008.8 2135.00  5012.3 2135.00  5012.5 2135.50
  5028.3 2137.81  5033.4 2137.25  5041.0 2139.80  5051.1 2140.95  5122.1 2143.09
  5155.0 2144.68  5182.9 2146.88  5264.0 2155.62  5271.6 2157.23  5304.5 2159.69
#Mann=3,-1,0
  4680.2    0.07       0  5008.5    0.05       0  5012.5    0.07       0
Bank Sta=5008.5,5012.5
Exp/Cntr=0.3,0.1

Type RM Length L Ch R = 1,515,0,0,0
BEGIN DESCRIPTION:
Stream0234 1.0
END DESCRIPTION:
XS GIS Cut Line= 3
      1805425.02     13891025.01      1805175.00     13890875.00
      1805074.98     13890824.99
#Sta/Elev= 30
  4712.8 2146.35  4742.0 2145.09  4763.4 2143.33  4818.3 2140.92  4861.9 2139.02
  4880.0 2138.49  4887.8 2137.38  4901.4 2136.45  4932.5 2133.50  4946.1 2132.94
  4953.8 2133.54  4959.7 2132.75  4969.4 2132.97  4981.1 2131.59  4990.8 2131.44
  4999.5 2130.94  4999.7 2130.44  5003.2 2130.44  5003.5 2130.94  5012.8 2131.04
  5018.4 2131.38  5026.7 2132.42  5031.6 2133.63  5035.1 2134.49  5040.7 2135.34
  5071.5 2143.29  5093.8 2144.21  5102.2 2145.02  5107.8 2145.98  5116.2 2146.42
#Mann=6,-1,0
  4712.8     0.1       0  4818.3    0.07       0  4861.9     0.1       0
  4999.5    0.05       0  5003.5     0.1       0  5031.6    0.07       0
Bank Sta=4999.5,5003.5
Exp/Cntr=0.3,0.1

Chan Stop Cuts=-1