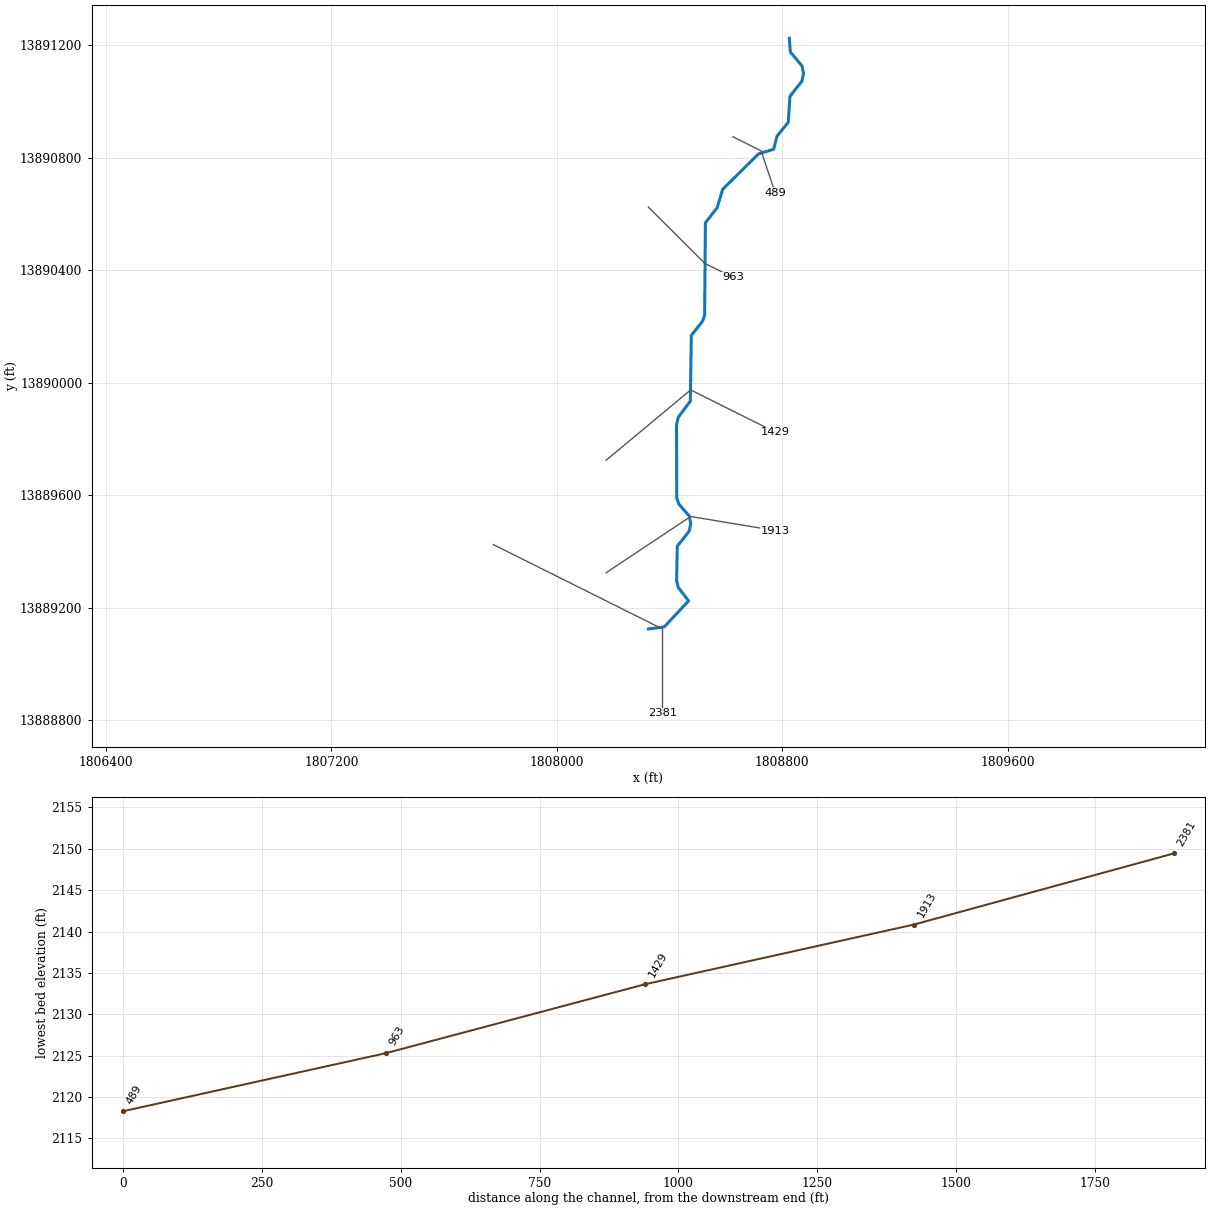
--- Stream0235.prj (project) ---

Proj Title=Stream0235 Base Level Engineering
Current Plan=p01
Default Exp/Contr=0.3,0.1
English Units
Geom File=g01
Flow File=f01
Plan File=p01
BEGIN DESCRIPTION:
Stream0235
END DESCRIPTION:

--- Stream0235.p01 (plan) ---

Plan Title=Multiple Run
Short Identifier=Multiple
Geom File=g01
Flow File=f01
Subcritical Flow
K Sum by GR= 0
Std Step Tol= 0.01
Critical Tol= 0.01
Num of Std Step Trials= 20
Max Error Tol= 0.3
Flow Tol Ratio= 0.001
Split Flow NTrial= 30
Split Flow Tol= 0.02
Split Flow Ratio= 0.02
Log Output Level= 0
Friction Slope Method= 1
Unsteady Friction Slope Method= 2
Unsteady Bridges Friction Slope Method= 1
Parabolic Critical Depth
Global Vel Dist=  1 , 1 , 1
Global Log Level= 0
CheckData=True
Encroach Param= -1, 0, 0, 0
BEGIN DESCRIPTION:
Multiple Run
END DESCRIPTION:

--- Stream0235.f01 (steady flow) ---

Flow Title=Multiple
Number of Profiles=7
Profile Names=10-year,25-year,50-year,1pct_min,100-year,1pct_plu,500-year
River Rch & RM= Stream0235,Reach-1,2381
     615    1019    1392     923    1841    3673    3176
Boundary for River Rch & Prof#=Stream0235,Reach-1,1
Up Type=0
Dn Type=3
Dn Slope=0.005
Boundary for River Rch & Prof#=Stream0235,Reach-1,2
Up Type=0
Dn Type=3
Dn Slope=0.005
Boundary for River Rch & Prof#=Stream0235,Reach-1,3
Up Type=0
Dn Type=3
Dn Slope=0.005
Boundary for River Rch & Prof#=Stream0235,Reach-1,4
Up Type=0
Dn Type=3
Dn Slope=0.005
Boundary for River Rch & Prof#=Stream0235,Reach-1,5
Up Type=0
Dn Type=3
Dn Slope=0.005
Boundary for River Rch & Prof#=Stream0235,Reach-1,6
Up Type=0
Dn Type=3
Dn Slope=0.005
Boundary for River Rch & Prof#=Stream0235,Reach-1,7
Up Type=0
Dn Type=3
Dn Slope=0.005

--- Stream0235.g01 (geometry) ---

Geom Title=Existing Conditions

River Reach=Stream0235,Reach-1
Reach XY= 30
      1808325.00     13889125.00      1808381.27     13889132.76
      1808467.70     13889224.89      1808431.03     13889272.55
      1808425.17     13889294.99      1808427.28     13889419.07
      1808469.62     13889472.82      1808475.40     13889500.00
      1808469.62     13889527.18      1808433.19     13889568.92
      1808425.54     13889590.21      1808424.80     13889850.08
      1808430.75     13889877.33      1808473.78     13889935.50
      1808477.26     13890169.06      1808516.86     13890218.94
      1808524.48     13890240.22      1808527.24     13890569.07
      1808568.86     13890622.83      1808588.62     13890688.22
      1808715.58     13890814.11      1808769.41     13890830.61
      1808781.28     13890876.84      1808821.19     13890926.56
      1808827.38     13891019.03      1808869.64     13891072.81
      1808875.47     13891100.00      1808869.88     13891127.25
      1808828.69     13891176.49      1808825.00     13891225.00

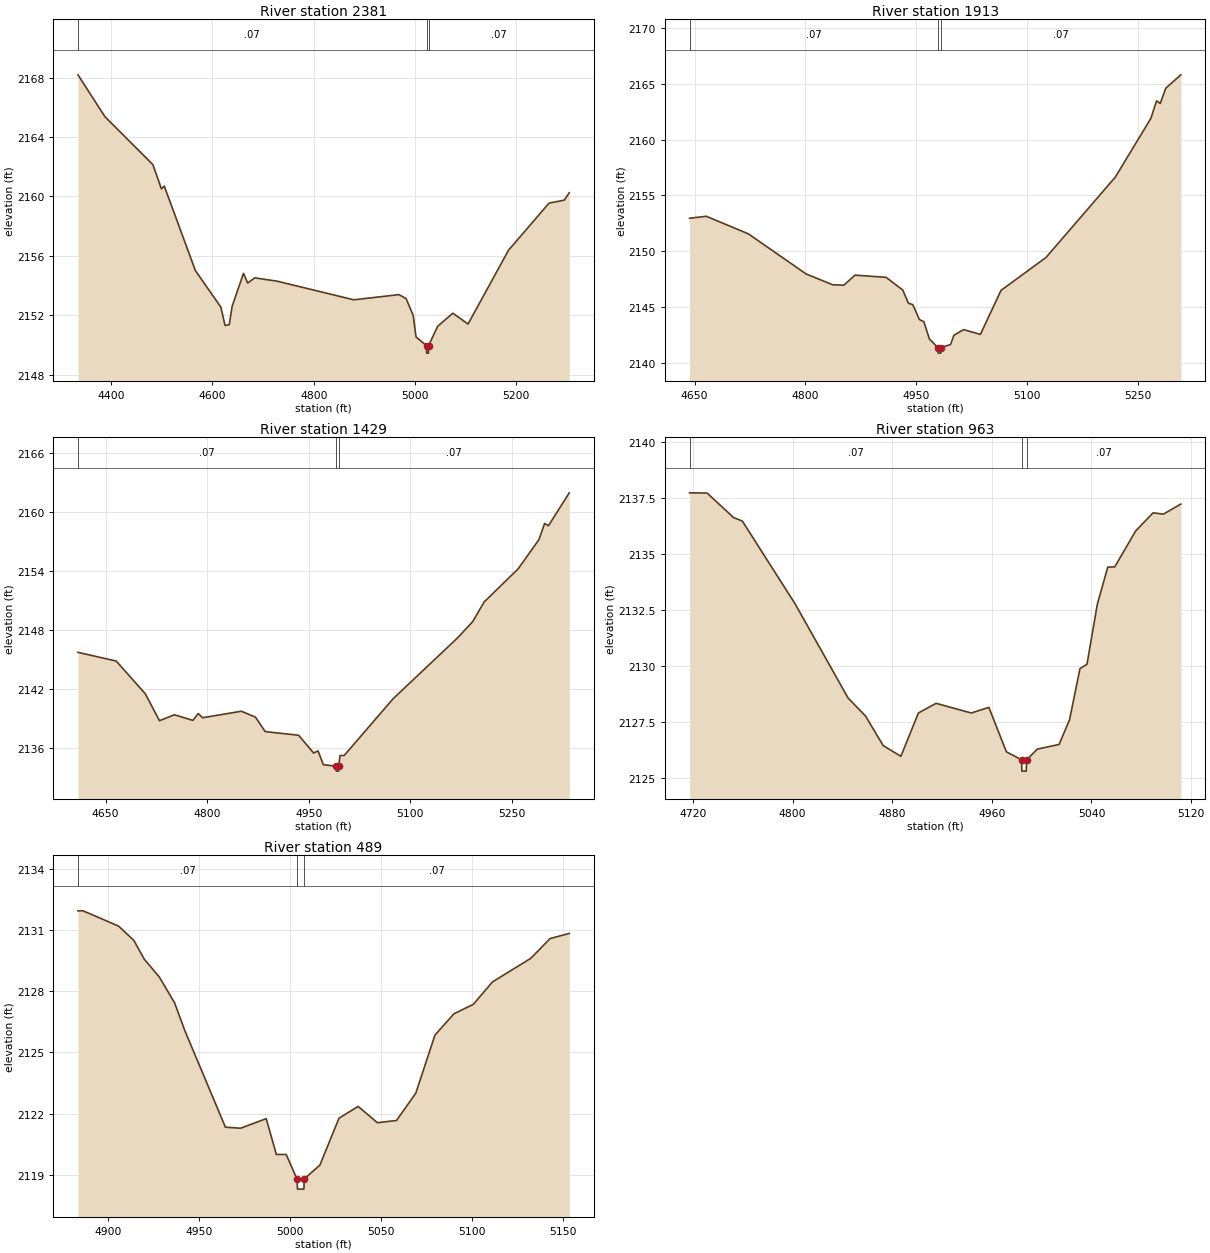
Type RM Length L Ch R = 1,2381,468,468,468
BEGIN DESCRIPTION:
Stream0235 5.0
END DESCRIPTION:
XS GIS Cut Line= 3
      1807775.03     13889424.98      1808375.00     13889125.00
      1808375.00     13888824.98
#Sta/Elev= 30
  4334.2 2168.19  4387.3 2165.38  4482.3 2162.14  4499.1 2160.51  4504.7 2160.70
  4566.2 2155.01  4616.5 2152.55  4624.9 2151.31  4633.2 2151.37  4638.8 2152.60
  4661.2 2154.82  4669.6 2154.17  4683.5 2154.52  4728.3 2154.29  4879.2 2153.04
  4968.6 2153.39  4982.6 2153.12  4996.6 2151.99  5002.2 2150.54  5023.0 2149.95
  5023.2 2149.45  5026.7 2149.45  5027.0 2149.95  5045.0 2151.26  5075.0 2152.14
  5105.0 2151.41  5185.0 2156.38  5265.0 2159.55  5295.0 2159.75  5305.0 2160.25
#Mann=3,-1,0
  4334.2    0.07       0  5023.0    0.05       0  5027.0    0.07       0
Bank Sta=5023,5027
Exp/Cntr=0.3,0.1

Type RM Length L Ch R = 1,1913,484,484,484
BEGIN DESCRIPTION:
Stream0235 4.0
END DESCRIPTION:
XS GIS Cut Line= 3
      1808174.98     13889324.99      1808475.00     13889525.00
      1808774.99     13889475.00
#Sta/Elev= 30
  4643.3 2152.95  4665.9 2153.13  4722.9 2151.55  4801.1 2147.95  4837.1 2146.98
  4852.1 2146.95  4867.2 2147.85  4909.2 2147.65  4931.8 2146.51  4939.3 2145.33
  4945.3 2145.20  4954.3 2143.86  4960.3 2143.67  4967.8 2142.12  4979.3 2141.35
  4979.6 2140.85  4983.1 2140.85  4983.3 2141.35  4996.4 2141.62  5000.9 2142.45
  5014.0 2142.96  5036.8 2142.53  5064.7 2146.48  5125.5 2149.43  5219.3 2156.64
  5267.5 2161.92  5275.1 2163.48  5280.1 2163.25  5287.7 2164.63  5308.0 2165.82
#Mann=3,-1,0
  4643.3    0.07       0  4979.3    0.05       0  4983.3    0.07       0
Bank Sta=4979.3,4983.3
Exp/Cntr=0.3,0.1

Type RM Length L Ch R = 1,1429,466,466,466
BEGIN DESCRIPTION:
Stream0235 3.0
END DESCRIPTION:
XS GIS Cut Line= 3
      1808175.03     13889725.03      1808475.00     13889975.00
      1808775.02     13889824.99
#Sta/Elev= 30
  4609.1 2145.72  4665.7 2144.83  4708.6 2141.50  4729.5 2138.77  4751.6 2139.37
  4778.9 2138.80  4786.7 2139.50  4793.3 2139.07  4850.5 2139.73  4871.4 2139.13
  4885.7 2137.66  4935.1 2137.29  4957.3 2135.48  4963.8 2135.70  4971.6 2134.30
  4990.4 2134.14  4990.7 2133.64  4994.2 2133.64  4994.4 2134.14  4996.3 2135.23
  5002.4 2135.23  5075.0 2141.02  5170.1 2147.20  5192.4 2148.85  5209.2 2150.84
  5259.5 2154.21  5290.3 2157.19  5298.6 2158.83  5304.2 2158.59  5335.0 2161.94
#Mann=3,-1,0
  4609.1    0.07       0  4990.4    0.05       0  4994.4    0.07       0
Bank Sta=4990.4,4994.4
Exp/Cntr=0.3,0.1

Type RM Length L Ch R = 1,963,474,474,474
BEGIN DESCRIPTION:
Stream0235 2.0
END DESCRIPTION:
XS GIS Cut Line= 3
      1808325.02     13890624.98      1808525.00     13890425.00
      1808624.98     13890375.01
#Sta/Elev= 30
  4717.2 2137.72  4731.3 2137.71  4752.5 2136.62  4759.6 2136.46  4802.0 2132.77
  4844.5 2128.58  4858.6 2127.77  4872.7 2126.46  4886.9 2125.98  4901.0 2127.91
  4915.2 2128.34  4943.5 2127.91  4957.6 2128.16  4971.7 2126.18  4983.9 2125.82
  4984.1 2125.32  4987.6 2125.32  4987.9 2125.82  4996.5 2126.30  5014.0 2126.51
  5022.4 2127.61  5030.8 2129.89  5036.4 2130.08  5044.7 2132.75  5053.1 2134.41
  5058.7 2134.42  5075.5 2136.02  5089.5 2136.83  5097.8 2136.77  5111.8 2137.22
#Mann=3,-1,0
  4717.2    0.07       0  4983.9    0.05       0  4987.9    0.07       0
Bank Sta=4983.9,4987.9
Exp/Cntr=0.3,0.1

Type RM Length L Ch R = 1,489,0,0,0
BEGIN DESCRIPTION:
Stream0235 1.0
END DESCRIPTION:
XS GIS Cut Line= 3
      1808625.02     13890874.99      1808725.00     13890825.00
      1808775.00     13890674.99
#Sta/Elev= 30
  4883.6 2131.95  4886.4 2131.95  4905.9 2131.20  4914.3 2130.50  4919.9 2129.59
  4928.3 2128.70  4936.7 2127.43  4942.3 2126.07  4964.6 2121.33  4973.0 2121.28
  4987.0 2121.75  4992.6 2119.99  4998.0 2119.99  5003.9 2118.79  5004.2 2118.29
  5007.7 2118.29  5007.9 2118.79  5016.5 2119.47  5027.0 2121.77  5037.5 2122.35
  5048.1 2121.55  5058.6 2121.66  5069.2 2123.00  5079.7 2125.85  5090.2 2126.90
  5100.8 2127.36  5111.3 2128.46  5132.4 2129.62  5143.0 2130.59  5153.5 2130.84
#Mann=3,-1,0
  4883.6    0.07       0  5003.9    0.05       0  5007.9    0.07       0
Bank Sta=5003.9,5007.9
Exp/Cntr=0.3,0.1

Chan Stop Cuts=-1