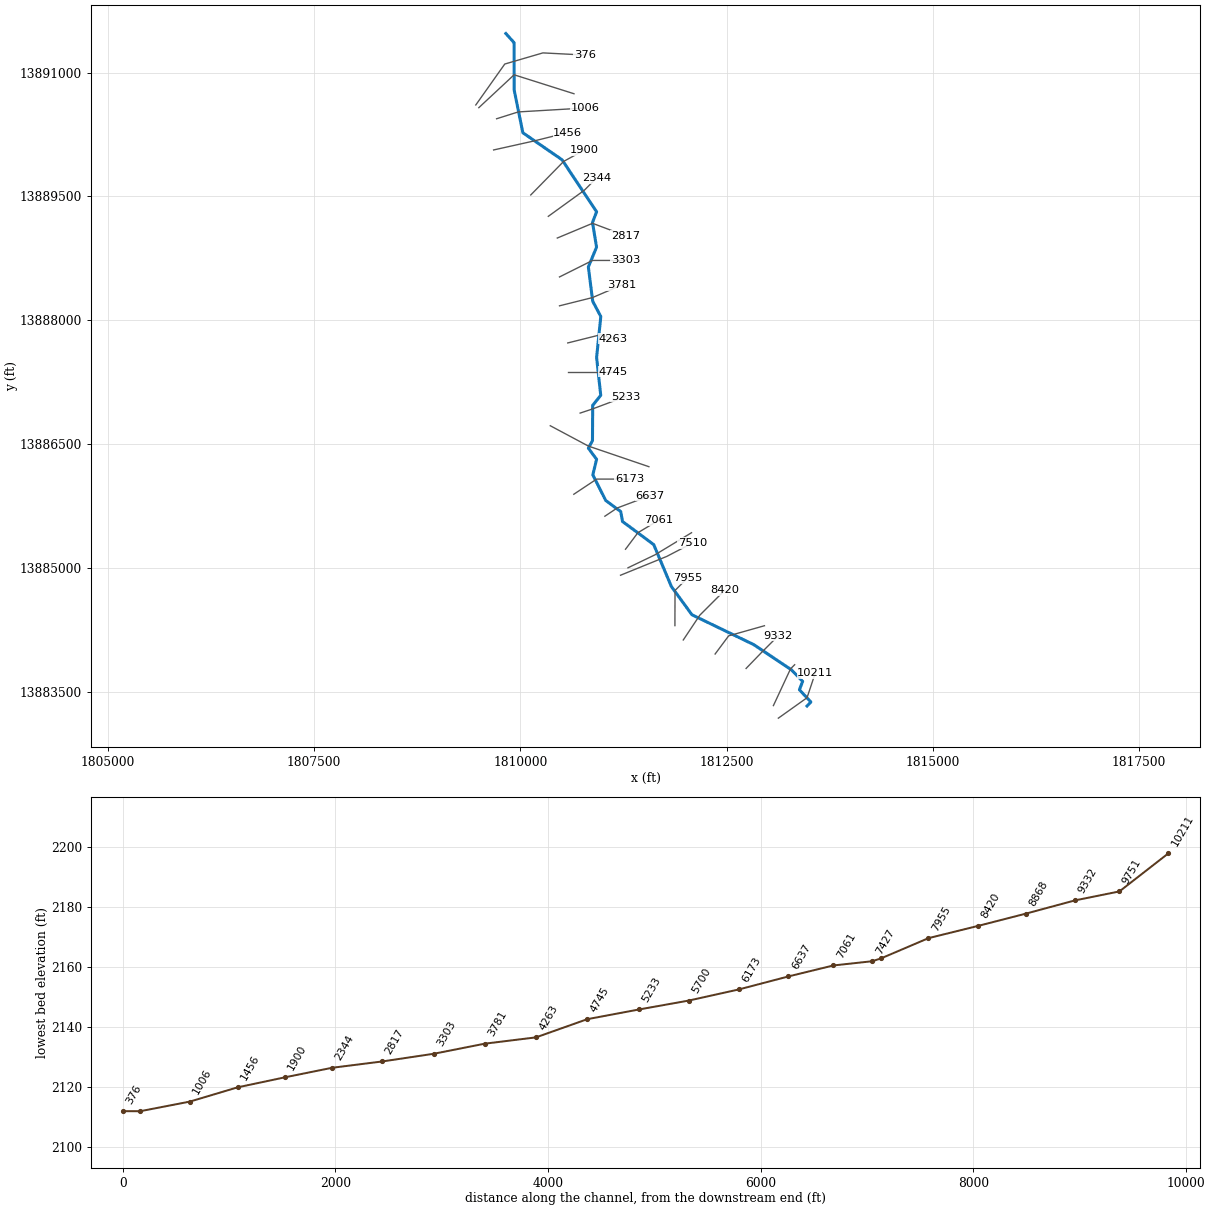
--- Stream0236.prj (project) ---

Proj Title=Stream0236 Base Level Engineering
Current Plan=p01
Default Exp/Contr=0.3,0.1
English Units
Geom File=g01
Flow File=f01
Plan File=p01
BEGIN DESCRIPTION:
Stream0236
END DESCRIPTION:

--- Stream0236.p01 (plan) ---

Plan Title=Multiple Run
Short Identifier=Multiple
Geom File=g01
Flow File=f01
Subcritical Flow
K Sum by GR= 0
Std Step Tol= 0.01
Critical Tol= 0.01
Num of Std Step Trials= 20
Max Error Tol= 0.3
Flow Tol Ratio= 0.001
Split Flow NTrial= 30
Split Flow Tol= 0.02
Split Flow Ratio= 0.02
Log Output Level= 0
Friction Slope Method= 1
Unsteady Friction Slope Method= 2
Unsteady Bridges Friction Slope Method= 1
Parabolic Critical Depth
Global Vel Dist=  1 , 1 , 1
Global Log Level= 0
CheckData=True
Encroach Param= -1, 0, 0, 0
BEGIN DESCRIPTION:
Multiple Run
END DESCRIPTION:

--- Stream0236.f01 (steady flow) ---

Flow Title=Multiple
Number of Profiles=7
Profile Names=10-year,25-year,50-year,1pct_min,100-year,1pct_plu,500-year
River Rch & RM= Stream0236,Reach-1,10211
     924    1561    2161    1446    2886    5758    5087
River Rch & RM= Stream0236,Reach-1,7510
    1391    2407    3384    2296    4582    9143    8312
River Rch & RM= Stream0236,Reach-1,5700
    1647    2875    4068    2777    5540   11053   10167
River Rch & RM= Stream0236,Reach-1,5233
    2042    3595    5112    3503    6990   13947   12936
Boundary for River Rch & Prof#=Stream0236,Reach-1,1
Up Type=0
Dn Type=3
Dn Slope=0.005
Boundary for River Rch & Prof#=Stream0236,Reach-1,2
Up Type=0
Dn Type=3
Dn Slope=0.005
Boundary for River Rch & Prof#=Stream0236,Reach-1,3
Up Type=0
Dn Type=3
Dn Slope=0.005
Boundary for River Rch & Prof#=Stream0236,Reach-1,4
Up Type=0
Dn Type=3
Dn Slope=0.005
Boundary for River Rch & Prof#=Stream0236,Reach-1,5
Up Type=0
Dn Type=3
Dn Slope=0.005
Boundary for River Rch & Prof#=Stream0236,Reach-1,6
Up Type=0
Dn Type=3
Dn Slope=0.005
Boundary for River Rch & Prof#=Stream0236,Reach-1,7
Up Type=0
Dn Type=3
Dn Slope=0.005

--- Stream0236.g01 (geometry) ---

Geom Title=Existing Conditions

River Reach=Stream0236,Reach-1
Reach XY= 30
      1813475.00     13883325.00      1813522.02     13883373.19
      1813382.82     13883521.59      1813421.84     13883623.35
      1813284.68     13883764.22      1812827.42     13884069.46
      1812080.44     13884430.25      1811830.83     13884772.70
      1811616.87     13885281.07      1811238.26     13885561.35
      1811217.14     13885681.19      1811035.63     13885815.00
      1810878.67     13886126.58      1810924.45     13886314.38
      1810824.73     13886450.31      1810874.55     13886540.19
      1810877.02     13886969.16      1810974.61     13887090.16
      1810924.60     13887550.00      1810975.36     13888045.15
      1810877.24     13888230.93      1810824.61     13888645.13
      1810923.80     13888885.51      1810874.50     13889185.17
      1810924.67     13889314.34      1810505.37     13889945.48
      1810030.73     13890272.45      1809925.52     13890790.22
      1809923.98     13891364.58      1809825.00     13891475.00

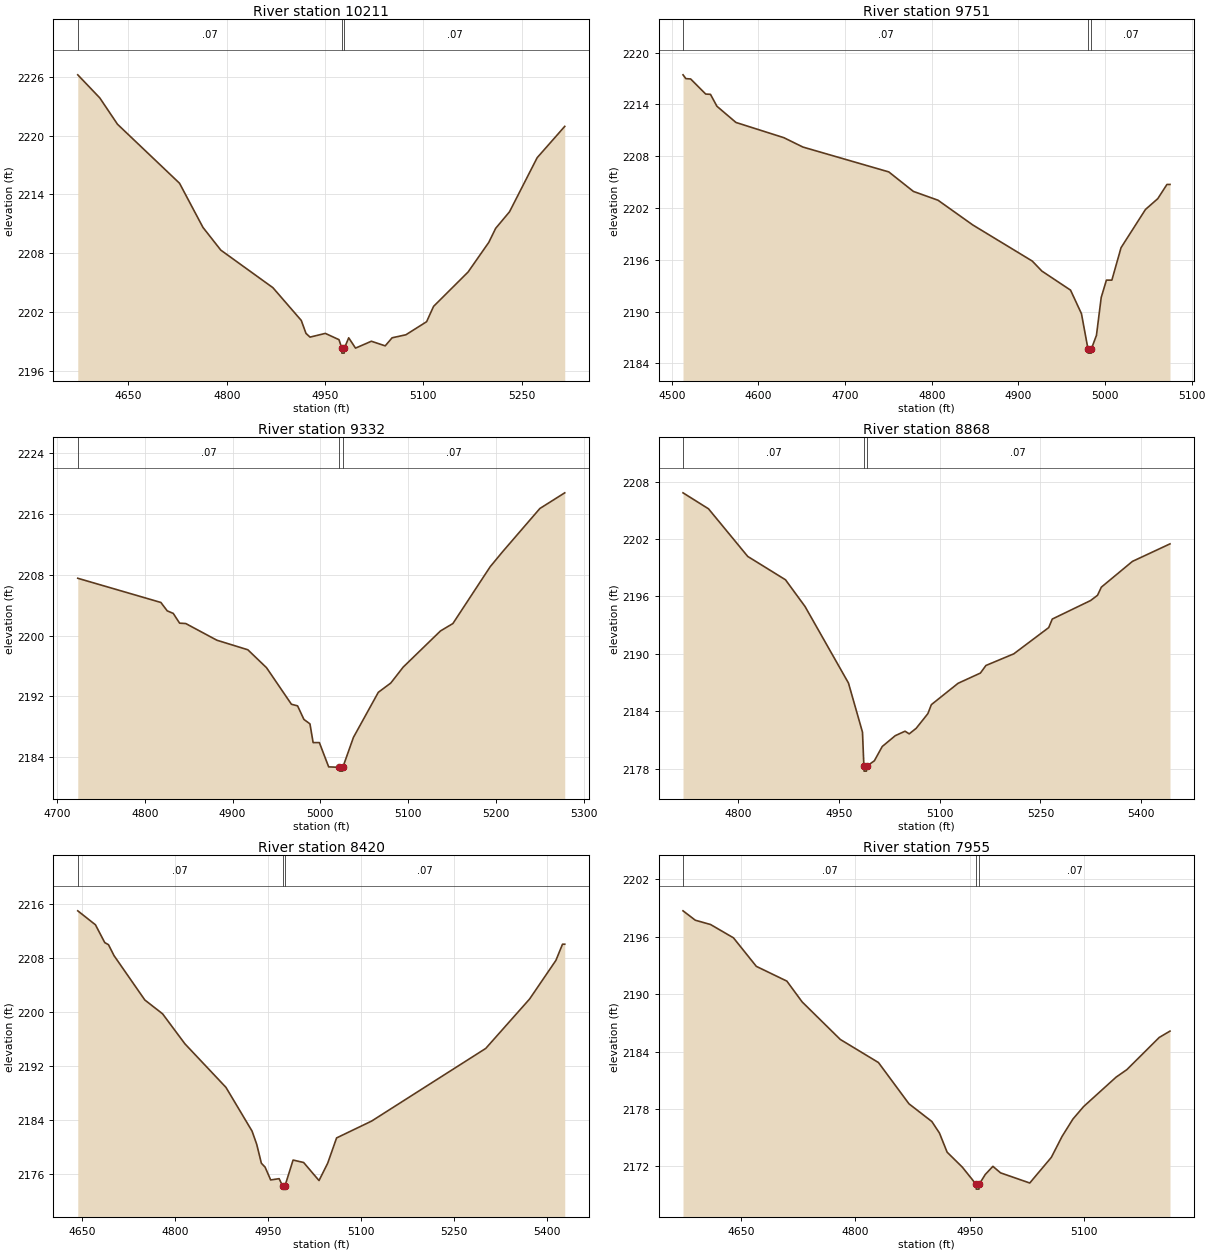
Type RM Length L Ch R = 1,10211,460,460,460
BEGIN DESCRIPTION:
Stream0236 22.0
END DESCRIPTION:
XS GIS Cut Line= 3
      1813127.16     13883177.31      1813475.00     13883425.00
      1813574.99     13883724.96
#Sta/Elev= 30
  4572.7 2226.18  4606.3 2223.83  4633.3 2221.15  4728.0 2215.14  4763.7 2210.65
  4791.0 2208.33  4870.6 2204.50  4913.8 2201.17  4921.0 2199.85  4927.2 2199.47
  4950.5 2199.85  4971.4 2199.21  4975.6 2198.34  4975.8 2197.84  4979.3 2197.84
  4979.6 2198.34  4986.2 2199.40  4996.6 2198.35  5020.8 2199.05  5041.9 2198.58
  5052.4 2199.40  5073.5 2199.71  5105.1 2201.04  5115.7 2202.60  5168.4 2206.10
  5200.0 2209.12  5210.5 2210.55  5231.6 2212.23  5273.8 2217.74  5315.9 2220.93
#Mann=3,-1,0
  4572.7    0.07       0  4975.6    0.05       0  4979.6    0.07       0
Bank Sta=4975.6,4979.6
Exp/Cntr=0.3,0.1

Type RM Length L Ch R = 1,9751,419,419,419
BEGIN DESCRIPTION:
Stream0236 21.0
END DESCRIPTION:
XS GIS Cut Line= 3
      1813067.42     13883329.57      1813275.00     13883775.00
      1813324.98     13883824.98
#Sta/Elev= 30
  4512.9 2217.43  4516.2 2216.99  4521.7 2216.95  4539.1 2215.20  4544.6 2215.17
  4552.0 2213.79  4574.0 2211.91  4629.2 2210.15  4651.3 2209.06  4750.4 2206.18
  4778.8 2203.92  4807.2 2202.90  4847.4 2200.03  4916.0 2195.85  4927.1 2194.69
  4960.2 2192.48  4972.8 2189.75  4980.3 2185.68  4980.5 2185.18  4984.0 2185.18
  4984.3 2185.68  4990.1 2187.24  4995.6 2191.63  5001.6 2193.64  5007.9 2193.64
  5018.5 2197.40  5046.7 2201.83  5060.9 2203.08  5071.5 2204.73  5075.0 2204.73
#Mann=3,-1,0
  4512.9    0.07       0  4980.3    0.05       0  4984.3    0.07       0
Bank Sta=4980.3,4984.3
Exp/Cntr=0.3,0.1

Type RM Length L Ch R = 1,9332,464,464,464
BEGIN DESCRIPTION:
Stream0236 20.0
END DESCRIPTION:
XS GIS Cut Line= 3
      1812736.31     13883779.90      1812925.00     13883975.00
      1813125.03     13884175.03
#Sta/Elev= 30
  4723.8 2207.54  4818.4 2204.36  4825.6 2203.26  4832.5 2202.92  4839.7 2201.64
  4846.7 2201.59  4882.1 2199.40  4917.4 2198.14  4938.7 2195.78  4967.0 2190.98
  4974.0 2190.77  4981.2 2188.99  4988.1 2188.40  4991.7 2185.94  4998.8 2185.94
  5009.4 2182.75  5021.5 2182.69  5021.7 2182.19  5025.2 2182.19  5025.5 2182.69
  5037.6 2186.63  5065.9 2192.55  5080.1 2193.77  5094.2 2195.86  5136.6 2200.61
  5150.8 2201.59  5193.2 2209.05  5207.3 2211.02  5249.8 2216.71  5278.1 2218.77
#Mann=3,-1,0
  4723.8    0.07       0  5021.5    0.05       0  5025.5    0.07       0
Bank Sta=5021.5,5025.5
Exp/Cntr=0.3,0.1

Type RM Length L Ch R = 1,8868,448,448,448
BEGIN DESCRIPTION:
Stream0236 19.0
END DESCRIPTION:
XS GIS Cut Line= 3
      1812360.90     13883954.75      1812525.00     13884175.00
      1812958.93     13884297.68
#Sta/Elev= 30
  4717.4 2206.82  4755.4 2205.15  4813.8 2200.18  4870.1 2197.74  4899.3 2194.94
  4963.9 2186.96  4984.8 2181.83  4986.9 2178.26  4987.2 2177.76  4990.7 2177.76
  4990.9 2178.26  5002.5 2178.84  5014.2 2180.33  5033.6 2181.46  5048.2 2181.93
  5054.4 2181.65  5064.8 2182.23  5082.2 2183.76  5087.4 2184.70  5127.2 2186.93
  5160.5 2188.00  5168.7 2188.79  5210.3 2190.01  5262.3 2192.75  5267.6 2193.64
  5324.6 2195.57  5335.0 2196.12  5340.7 2196.97  5387.0 2199.66  5443.0 2201.49
#Mann=3,-1,0
  4717.4    0.07       0  4986.9    0.05       0  4990.9    0.07       0
Bank Sta=4986.9,4990.9
Exp/Cntr=0.3,0.1

Type RM Length L Ch R = 1,8420,465,465,465
BEGIN DESCRIPTION:
Stream0236 18.0
END DESCRIPTION:
XS GIS Cut Line= 3
      1811975.02     13884125.04      1812175.00     13884425.00
      1812475.02     13884725.02
#Sta/Elev= 30
  4643.6 2214.95  4672.1 2212.88  4687.1 2210.24  4693.1 2209.93  4702.1 2208.30
  4751.7 2201.73  4780.3 2199.68  4816.3 2195.23  4882.4 2188.78  4924.5 2182.29
  4932.0 2180.33  4939.5 2177.53  4945.5 2176.95  4954.5 2175.05  4968.1 2175.24
  4973.6 2174.19  4973.8 2173.69  4977.3 2173.69  4977.6 2174.19  4990.6 2178.00
  5007.6 2177.64  5032.4 2174.96  5046.5 2177.56  5060.7 2181.28  5117.2 2183.78
  5301.1 2194.55  5371.8 2201.88  5414.2 2207.61  5424.8 2210.00  5428.4 2210.00
#Mann=3,-1,0
  4643.6    0.07       0  4973.6    0.05       0  4977.6    0.07       0
Bank Sta=4973.6,4977.6
Exp/Cntr=0.3,0.1

Type RM Length L Ch R = 1,7955,445,445,445
BEGIN DESCRIPTION:
Stream0236 17.0
END DESCRIPTION:
XS GIS Cut Line= 3
      1811873.68     13884298.90      1811875.00     13884725.00
      1812024.98     13884874.98
#Sta/Elev= 30
  4574.2 2198.69  4590.3 2197.71  4610.3 2197.26  4640.3 2195.87  4670.3 2192.89
  4710.3 2191.35  4730.3 2189.18  4780.3 2185.26  4830.3 2182.85  4870.3 2178.54
  4900.3 2176.69  4910.3 2175.48  4920.3 2173.49  4940.3 2171.92  4958.3 2170.13
  4958.5 2169.63  4962.0 2169.63  4962.3 2170.13  4970.3 2171.16  4980.3 2172.01
  4990.3 2171.33  5028.6 2170.27  5056.9 2172.95  5071.0 2175.14  5085.2 2176.95
  5099.3 2178.26  5141.7 2181.32  5155.9 2182.11  5198.3 2185.47  5212.4 2186.13
#Mann=3,-1,0
  4574.2    0.07       0  4958.3    0.05       0  4962.3    0.07       0
Bank Sta=4958.3,4962.3
Exp/Cntr=0.3,0.1

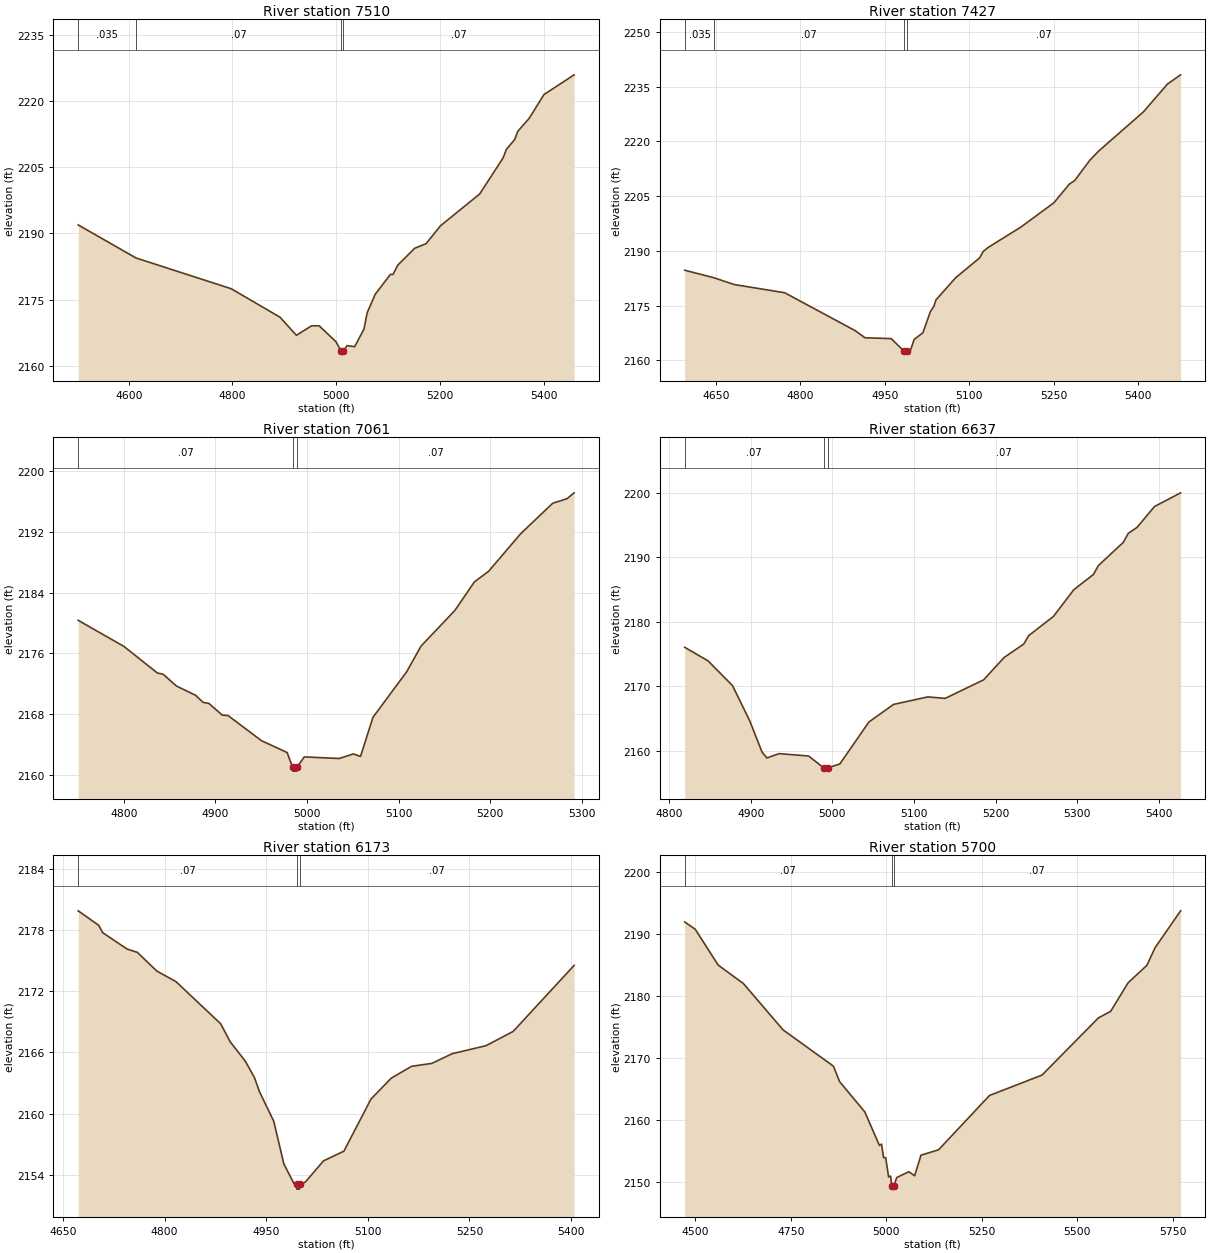
Type RM Length L Ch R = 1,7510,83,83,83
BEGIN DESCRIPTION:
Stream0236 16.1
END DESCRIPTION:
XS GIS Cut Line= 3
      1811214.53     13884909.66      1811774.41     13885137.52
      1812086.63     13885300.14
#Sta/Elev= 30
  4502.6 2191.92  4614.1 2184.44  4797.7 2177.48  4891.8 2171.04  4923.4 2166.95
  4952.8 2169.10  4967.3 2169.09  4999.7 2165.50  5009.4 2163.41  5009.8 2162.91
  5014.0 2163.41  5021.3 2164.61  5035.8 2164.37  5053.7 2168.34  5059.9 2172.03
  5075.3 2176.21  5104.7 2180.72  5109.7 2180.72  5119.0 2182.83  5151.5 2186.63
  5173.6 2187.68  5201.3 2191.72  5276.9 2198.92  5322.0 2207.07  5328.3 2208.99
  5344.5 2211.26  5350.4 2213.09  5372.5 2216.06  5400.9 2221.42  5459.1 2225.88
#Mann=4,-1,0
  4502.6   0.035       0  4614.1    0.07       0  5009.4    0.05       0
  5014.0    0.07       0
Bank Sta=5009.4,5014
Exp/Cntr=0.3,0.1

Type RM Length L Ch R = 1,7427,366,366,366
BEGIN DESCRIPTION:
Stream0236 16.0
END DESCRIPTION:
XS GIS Cut Line= 3
      1811304.87     13884999.85      1811633.41     13885157.58
      1812075.00     13885425.00
#Sta/Elev= 30
  4594.6 2184.67  4647.1 2182.58  4682.7 2180.74  4772.2 2178.50  4897.6 2168.09
  4914.7 2166.17  4961.4 2165.92  4984.3 2162.45  4984.6 2161.95  4988.5 2161.95
  4988.9 2162.45  4996.0 2162.92  5002.1 2165.69  5017.6 2167.53  5031.1 2173.40
  5036.9 2174.69  5040.9 2176.54  5075.8 2182.61  5118.4 2188.05  5124.6 2189.77
  5133.9 2190.95  5192.1 2196.54  5250.3 2203.15  5277.5 2208.24  5287.1 2209.23
  5314.3 2214.85  5329.8 2217.32  5409.4 2228.08  5452.0 2235.69  5475.3 2238.21
#Mann=4,-1,0
  4594.6   0.035       0  4647.1    0.07       0  4984.3    0.05       0
  4988.9    0.07       0
Bank Sta=4984.3,4988.9
Exp/Cntr=0.3,0.1

Type RM Length L Ch R = 1,7061,424,424,424
BEGIN DESCRIPTION:
Stream0236 15.0
END DESCRIPTION:
XS GIS Cut Line= 3
      1811274.99     13885224.99      1811425.00     13885425.00
      1811675.04     13885575.02
#Sta/Elev= 30
  4750.2 2180.36  4800.2 2176.92  4836.7 2173.43  4842.9 2173.28  4857.5 2171.72
  4878.3 2170.51  4886.7 2169.57  4892.9 2169.44  4907.5 2167.90  4913.8 2167.85
  4950.2 2164.55  4978.3 2162.99  4984.4 2161.04  4984.7 2160.54  4988.7 2160.54
  4989.0 2161.04  4997.1 2162.41  5035.2 2162.20  5050.7 2162.80  5058.5 2162.47
  5072.1 2167.61  5109.1 2173.63  5124.6 2176.97  5161.5 2181.65  5182.9 2185.41
  5198.5 2186.81  5233.4 2191.74  5268.4 2195.74  5284.0 2196.34  5291.8 2197.11
#Mann=3,-1,0
  4750.2    0.07       0  4984.4    0.05       0  4989.0    0.07       0
Bank Sta=4984.4,4989
Exp/Cntr=0.3,0.1

Type RM Length L Ch R = 1,6637,464,464,464
BEGIN DESCRIPTION:
Stream0236 14.0
END DESCRIPTION:
XS GIS Cut Line= 3
      1811024.98     13885624.99      1811175.00     13885725.00
      1811575.00     13885875.00
#Sta/Elev= 30
  4819.2 2176.05  4847.8 2173.95  4877.8 2170.12  4898.8 2164.69  4913.9 2159.85
  4919.9 2158.92  4934.9 2159.59  4971.0 2159.22  4989.6 2157.38  4990.0 2156.88
  4994.0 2156.88  4994.3 2157.38  5009.3 2157.99  5044.9 2164.49  5075.1 2167.21
  5117.0 2168.37  5138.3 2168.14  5185.5 2171.02  5210.4 2174.46  5234.5 2176.55
  5240.7 2177.87  5270.9 2180.82  5295.9 2184.97  5319.9 2187.32  5326.1 2188.72
  5356.4 2192.28  5362.6 2193.69  5373.3 2194.61  5394.7 2197.84  5426.7 2199.96
#Mann=3,-1,0
  4819.2    0.07       0  4989.6    0.05       0  4994.3    0.07       0
Bank Sta=4989.6,4994.3
Exp/Cntr=0.3,0.1

Type RM Length L Ch R = 1,6173,473,473,473
BEGIN DESCRIPTION:
Stream0236 13.0
END DESCRIPTION:
XS GIS Cut Line= 3
      1810648.32     13885890.98      1810925.00     13886075.00
      1811325.01     13886075.00
#Sta/Elev= 30
  4672.4 2179.92  4702.6 2178.50  4708.6 2177.77  4744.7 2176.16  4759.7 2175.84
  4788.5 2174.00  4816.8 2172.96  4882.9 2168.81  4896.6 2167.07  4919.0 2165.16
  4932.6 2163.54  4940.1 2162.14  4961.1 2159.25  4976.1 2155.04  4991.2 2153.09
  4994.8 2153.07  4995.2 2152.57  4999.2 2152.57  4999.5 2153.07  5007.2 2153.23
  5034.7 2155.35  5064.7 2156.30  5104.7 2161.42  5134.7 2163.48  5164.7 2164.64
  5194.7 2164.93  5224.7 2165.88  5274.7 2166.67  5314.7 2168.07  5404.7 2174.56
#Mann=3,-1,0
  4672.4    0.07       0  4994.8    0.05       0  4999.5    0.07       0
Bank Sta=4994.8,4999.5
Exp/Cntr=0.3,0.1

Type RM Length L Ch R = 1,5700,467,467,467
BEGIN DESCRIPTION:
Stream0236 12.0
END DESCRIPTION:
XS GIS Cut Line= 3
      1810363.10     13886721.63      1810825.00     13886475.00
      1811558.49     13886225.13
#Sta/Elev= 30
  4472.4 2191.90  4500.0 2190.74  4560.2 2184.95  4626.0 2181.99  4730.1 2174.51
  4861.8 2168.67  4878.1 2166.17  4944.0 2161.30  4982.2 2155.90  4987.9 2156.11
  4993.2 2153.92  4998.7 2153.92  5006.4 2150.81  5011.7 2150.95  5014.4 2149.35
  5014.8 2148.85  5019.8 2149.35  5027.7 2150.72  5059.4 2151.66  5074.4 2151.00
  5091.1 2154.32  5137.1 2155.19  5270.7 2163.95  5408.0 2167.23  5555.9 2176.46
  5587.6 2177.49  5633.5 2182.11  5682.7 2184.92  5703.8 2187.74  5770.9 2193.70
#Mann=3,-1,0
  4472.4    0.07       0  5014.4    0.05       0  5019.8    0.07       0
Bank Sta=5014.4,5019.8
Exp/Cntr=0.3,0.1

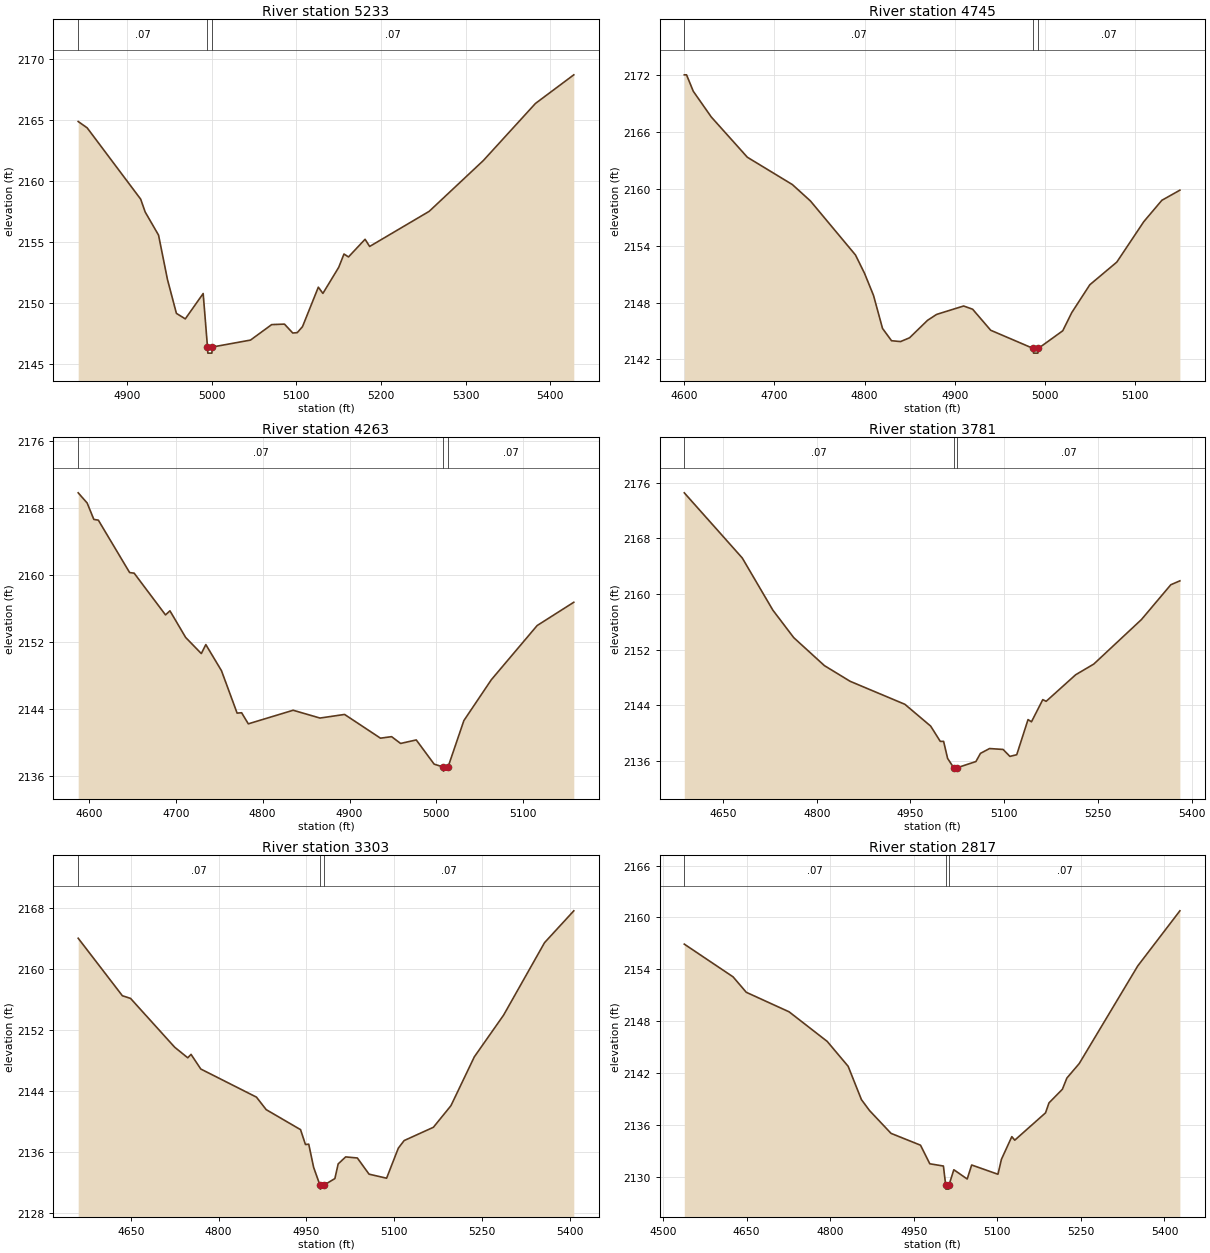
Type RM Length L Ch R = 1,5233,488,488,488
BEGIN DESCRIPTION:
Stream0236 11.0
END DESCRIPTION:
XS GIS Cut Line= 3
      1810724.97     13886874.99      1810875.00     13886925.00
      1811274.95     13887074.98
#Sta/Elev= 30
  4842.4 2164.89  4853.0 2164.37  4916.2 2158.52  4921.5 2157.47  4937.3 2155.57
  4947.8 2151.94  4958.4 2149.15  4968.9 2148.70  4990.0 2150.78  4995.1 2146.39
  4995.5 2145.89  5000.3 2145.89  5000.8 2146.39  5045.9 2146.96  5070.9 2148.23
  5086.0 2148.27  5095.8 2147.54  5101.1 2147.57  5107.3 2148.06  5126.0 2151.30
  5131.4 2150.79  5150.1 2152.93  5156.3 2154.02  5161.6 2153.78  5181.2 2155.23
  5186.6 2154.64  5256.9 2157.52  5320.9 2161.69  5382.4 2166.37  5427.7 2168.72
#Mann=3,-1,0
  4842.4    0.07       0  4995.1    0.05       0  5000.8    0.07       0
Bank Sta=4995.1,5000.8
Exp/Cntr=0.3,0.1

Type RM Length L Ch R = 1,4745,482,482,482
BEGIN DESCRIPTION:
Stream0236 10.0
END DESCRIPTION:
XS GIS Cut Line= 3
      1810574.98     13887375.00      1810975.00     13887375.00
      1811124.98     13887375.00
#Sta/Elev= 30
  4599.9 2172.06  4602.4 2172.06  4609.9 2170.32  4629.9 2167.60  4669.9 2163.35
  4719.9 2160.46  4739.9 2158.73  4789.9 2153.02  4799.9 2151.09  4809.9 2148.75
  4819.9 2145.26  4829.9 2143.96  4839.9 2143.87  4849.9 2144.27  4869.9 2146.12
  4879.9 2146.74  4909.9 2147.63  4919.9 2147.29  4939.9 2145.07  4987.0 2143.15
  4987.5 2142.65  4992.3 2142.65  4992.8 2143.15  5019.9 2145.01  5029.9 2146.93
  5049.9 2149.87  5079.9 2152.27  5109.9 2156.55  5129.9 2158.80  5149.9 2159.87
#Mann=3,-1,0
  4599.9    0.07       0  4987.0    0.05       0  4992.8    0.07       0
Bank Sta=4987,4992.8
Exp/Cntr=0.3,0.1

Type RM Length L Ch R = 1,4263,482,482,482
BEGIN DESCRIPTION:
Stream0236 9.0
END DESCRIPTION:
XS GIS Cut Line= 3
      1810575.03     13887725.01      1810975.00     13887825.00
      1811125.00     13887775.00
#Sta/Elev= 30
  4587.7 2169.79  4598.0 2168.58  4605.7 2166.62  4610.9 2166.53  4646.9 2160.28
  4652.1 2160.21  4688.2 2155.23  4693.3 2155.72  4711.4 2152.54  4729.4 2150.62
  4734.6 2151.69  4752.6 2148.58  4770.6 2143.52  4775.8 2143.56  4783.5 2142.24
  4835.1 2143.86  4866.0 2142.93  4894.3 2143.36  4935.6 2140.53  4948.4 2140.71
  4958.8 2139.90  4976.8 2140.32  4997.4 2137.43  5007.6 2137.10  5008.1 2136.60
  5013.4 2137.10  5031.6 2142.63  5063.2 2147.50  5115.9 2153.96  5158.1 2156.74
#Mann=3,-1,0
  4587.7    0.07       0  5007.6    0.05       0  5013.4    0.07       0
Bank Sta=5007.6,5013.4
Exp/Cntr=0.3,0.1

Type RM Length L Ch R = 1,3781,478,478,478
BEGIN DESCRIPTION:
Stream0236 8.0
END DESCRIPTION:
XS GIS Cut Line= 3
      1810474.99     13888175.00      1810875.00     13888275.00
      1811225.00     13888425.00
#Sta/Elev= 30
  4588.1 2174.56  4680.9 2165.18  4729.8 2157.68  4763.3 2153.71  4812.3 2149.69
  4853.5 2147.43  4941.1 2144.12  4982.4 2140.98  4997.8 2138.78  5003.1 2138.78
  5009.5 2136.33  5019.2 2135.00  5019.7 2134.50  5024.7 2134.50  5025.2 2135.00
  5054.8 2135.88  5062.1 2137.06  5076.6 2137.75  5098.3 2137.62  5109.2 2136.62
  5120.1 2136.86  5138.2 2141.92  5143.7 2141.60  5161.8 2144.79  5167.2 2144.55
  5214.4 2148.37  5243.4 2149.91  5319.6 2156.31  5366.7 2161.33  5381.2 2161.89
#Mann=3,-1,0
  4588.1    0.07       0  5019.2    0.05       0  5025.2    0.07       0
Bank Sta=5019.2,5025.2
Exp/Cntr=0.3,0.1

Type RM Length L Ch R = 1,3303,486,486,486
BEGIN DESCRIPTION:
Stream0236 7.0
END DESCRIPTION:
XS GIS Cut Line= 3
      1810474.99     13888525.00      1810875.00     13888725.00
      1811274.98     13888725.00
#Sta/Elev= 30
  4559.9 2164.01  4635.4 2156.48  4649.4 2156.13  4724.8 2149.74  4747.2 2148.35
  4752.8 2148.80  4769.5 2146.88  4864.6 2143.20  4881.3 2141.56  4940.0 2138.94
  4948.4 2136.99  4954.0 2137.04  4962.4 2133.99  4973.3 2131.65  4973.8 2131.15
  4979.4 2131.65  4998.7 2132.53  5004.3 2134.45  5017.1 2135.37  5037.1 2135.23
  5057.1 2133.11  5087.1 2132.58  5107.1 2136.51  5117.1 2137.51  5167.1 2139.25
  5197.1 2142.08  5237.1 2148.48  5287.1 2153.94  5357.1 2163.43  5407.1 2167.60
#Mann=3,-1,0
  4559.9    0.07       0  4973.3    0.05       0  4979.4    0.07       0
Bank Sta=4973.3,4979.4
Exp/Cntr=0.3,0.1

Type RM Length L Ch R = 1,2817,473,473,473
BEGIN DESCRIPTION:
Stream0236 6.0
END DESCRIPTION:
XS GIS Cut Line= 3
      1810448.25     13888996.68      1810875.00     13889175.00
      1811274.99     13889025.00
#Sta/Elev= 30
  4538.0 2156.91  4625.5 2153.13  4649.3 2151.34  4726.2 2149.08  4794.6 2145.66
  4832.2 2142.78  4856.0 2138.93  4870.5 2137.67  4909.1 2135.03  4962.1 2133.66
  4978.8 2131.51  5003.2 2131.25  5007.2 2129.08  5007.7 2128.58  5012.8 2128.58
  5013.3 2129.08  5021.9 2130.82  5045.9 2129.75  5053.9 2131.37  5101.1 2130.30
  5107.3 2132.02  5126.0 2134.65  5131.3 2134.24  5186.5 2137.40  5192.7 2138.55
  5216.8 2140.13  5224.8 2141.42  5247.0 2143.10  5352.1 2154.39  5427.7 2160.76
#Mann=3,-1,0
  4538.0    0.07       0  5007.2    0.05       0  5013.3    0.07       0
Bank Sta=5007.2,5013.3
Exp/Cntr=0.3,0.1

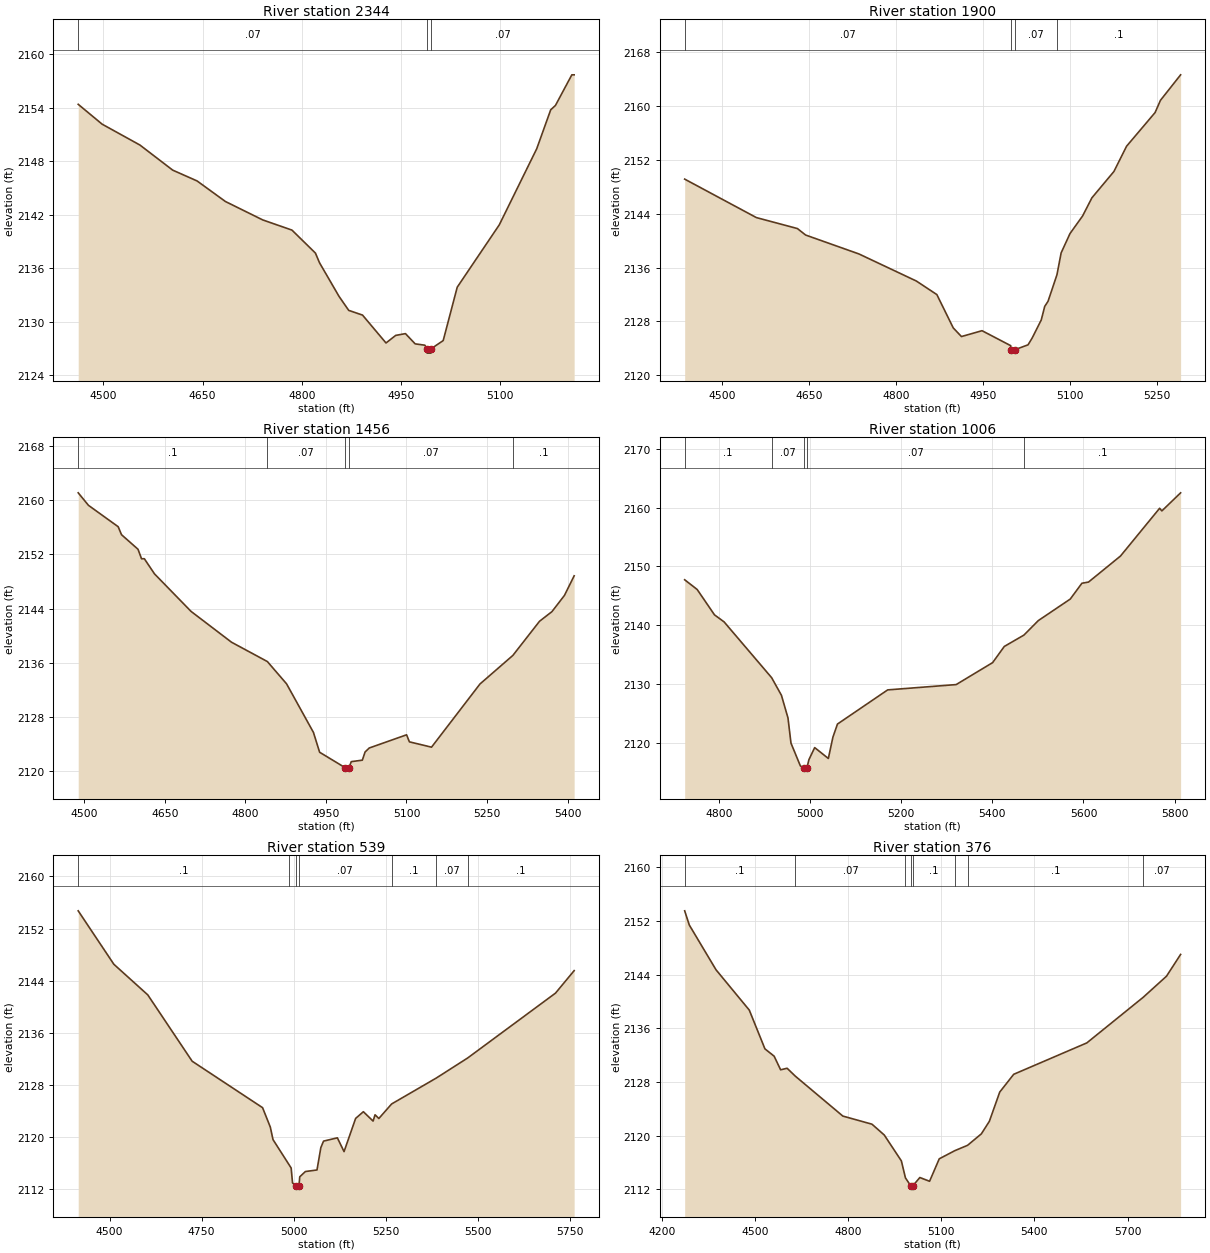
Type RM Length L Ch R = 1,2344,444,444,444
BEGIN DESCRIPTION:
Stream0236 5.0
END DESCRIPTION:
XS GIS Cut Line= 3
      1810339.41     13889259.65      1810775.00     13889575.00
      1810925.01     13889725.01
#Sta/Elev= 30
  4462.0 2154.40  4498.2 2152.17  4555.3 2149.83  4604.9 2147.01  4641.7 2145.80
  4684.6 2143.49  4741.1 2141.42  4785.2 2140.28  4820.7 2137.70  4826.9 2136.61
  4856.3 2132.85  4871.0 2131.27  4891.9 2130.74  4927.4 2127.61  4942.1 2128.46
  4956.8 2128.66  4971.5 2127.51  4986.2 2127.36  4989.1 2126.97  4989.6 2126.47
  4995.3 2126.47  4995.8 2126.97  5013.9 2127.88  5035.1 2133.87  5098.7 2140.87
  5155.3 2149.41  5176.5 2153.79  5183.6 2154.27  5208.4 2157.71  5211.9 2157.71
#Mann=3,-1,0
  4462.0    0.07       0  4989.1    0.05       0  4995.8    0.07       0
Bank Sta=4989.1,4995.8
Exp/Cntr=0.3,0.1

Type RM Length L Ch R = 1,1900,444,444,444
BEGIN DESCRIPTION:
Stream0236 4.0
END DESCRIPTION:
XS GIS Cut Line= 3
      1810126.52     13889518.58      1810525.00     13889925.00
      1810775.49     13890062.87
#Sta/Elev= 30
  4435.5 2149.12  4559.1 2143.41  4629.9 2141.78  4644.0 2140.82  4736.0 2138.01
  4835.0 2133.99  4870.3 2131.98  4898.6 2127.03  4912.7 2125.75  4948.2 2126.62
  4997.6 2124.40  4997.8 2123.79  4998.3 2123.29  5004.1 2123.29  5004.6 2123.79
  5027.5 2124.52  5034.5 2125.51  5050.3 2128.21  5056.3 2130.23  5062.0 2130.98
  5077.4 2134.93  5084.6 2138.17  5099.9 2141.04  5121.6 2143.65  5137.7 2146.35
  5175.6 2150.25  5197.4 2154.00  5246.6 2159.00  5255.8 2160.81  5290.6 2164.60
#Mann=4,-1,0
  4435.5    0.07       0  4997.8    0.05       0  5004.6    0.07       0
  5077.4     0.1       0
Bank Sta=4997.8,5004.6
Exp/Cntr=0.3,0.1

Type RM Length L Ch R = 1,1456,450,450,450
BEGIN DESCRIPTION:
Stream0236 3.0
END DESCRIPTION:
XS GIS Cut Line= 3
      1809676.35     13890064.06      1810175.00     13890175.00
      1810575.04     13890275.01
#Sta/Elev= 30
  4488.9 2161.10  4508.0 2159.25  4563.3 2156.09  4569.5 2154.91  4600.2 2152.76
  4606.8 2151.35  4612.0 2151.36  4630.9 2149.12  4699.0 2143.57  4774.4 2139.01
  4841.0 2136.16  4876.8 2132.86  4926.8 2125.68  4938.3 2122.75  4986.0 2120.46
  4986.5 2119.96  4992.9 2120.46  4997.2 2121.36  5017.8 2121.58  5022.9 2122.79
  5030.7 2123.38  5100.2 2125.33  5105.4 2124.29  5146.6 2123.50  5236.8 2132.84
  5298.1 2137.07  5347.6 2142.11  5370.8 2143.54  5394.0 2145.93  5412.1 2148.83
#Mann=5,-1,0
  4488.9     0.1       0  4841.0    0.07       0  4986.0    0.05       0
  4992.9    0.07       0  5298.1     0.1       0
Bank Sta=4986,4992.9
Exp/Cntr=0.3,0.1

Type RM Length L Ch R = 1,1006,467,467,467
BEGIN DESCRIPTION:
Stream0236 2.0
END DESCRIPTION:
XS GIS Cut Line= 3
      1809712.52     13890442.20      1809975.00     13890525.00
      1810786.77     13890572.66
#Sta/Elev= 30
  4724.8 2147.74  4752.2 2146.09  4790.3 2141.77  4811.3 2140.58  4915.7 2131.09
  4937.1 2128.11  4951.5 2124.26  4958.1 2119.97  4978.6 2116.12  4986.0 2115.71
  4986.5 2115.21  4993.0 2115.71  4997.4 2117.15  5010.1 2119.21  5040.1 2117.36
  5050.1 2120.98  5060.1 2123.21  5170.3 2129.02  5320.6 2129.92  5400.7 2133.66
  5426.2 2136.40  5469.4 2138.34  5500.9 2140.80  5571.0 2144.46  5596.6 2147.15
  5611.1 2147.35  5681.2 2151.77  5767.1 2159.89  5772.1 2159.45  5813.2 2162.52
#Mann=5,-1,0
  4724.8     0.1       0  4915.7    0.07       0  4986.0    0.05       0
  4993.0    0.07       0  5469.4     0.1       0
Bank Sta=4986,4993
Exp/Cntr=0.3,0.1

Type RM Length L Ch R = 1,539,163,163,163
BEGIN DESCRIPTION:
Stream0236 1.0
END DESCRIPTION:
XS GIS Cut Line= 3
      1809496.87     13890576.32      1809925.00     13890975.00
      1810650.31     13890745.40
#Sta/Elev= 30
  4415.0 2154.72  4511.7 2146.52  4603.8 2141.82  4724.2 2131.64  4915.3 2124.51
  4936.3 2121.53  4943.6 2119.61  4987.8 2115.70  4992.9 2115.25  4996.6 2112.96
  5007.0 2112.51  5007.5 2112.01  5014.0 2112.51  5016.2 2113.90  5031.5 2114.71
  5063.0 2114.95  5073.4 2118.38  5080.8 2119.38  5118.3 2119.88  5136.4 2117.77
  5167.8 2122.86  5188.8 2123.89  5215.2 2122.45  5220.5 2123.42  5230.8 2122.85
  5265.5 2125.08  5386.5 2129.05  5471.7 2132.13  5710.2 2142.09  5760.8 2145.54
#Mann=7,-1,0
  4415.0     0.1       0  4987.8    0.07       0  5007.0    0.05       0
  5014.0    0.07       0  5265.5     0.1       0  5386.5    0.07       0
  5471.7     0.1       0
Bank Sta=5007,5014
Exp/Cntr=0.3,0.1

Type RM Length L Ch R = 1,376,0,0,0
BEGIN DESCRIPTION:
Stream0236 0.0
END DESCRIPTION:
XS GIS Cut Line= 4
      1809460.44     13890609.41      1809811.54     13891105.40
      1810273.73     13891240.45      1810780.47     13891214.53
#Sta/Elev= 30
  4274.1 2153.52  4288.9 2151.41  4375.0 2144.73  4482.1 2138.72  4532.5 2132.94
  4562.1 2131.85  4583.0 2129.82  4603.9 2130.05  4630.6 2128.86  4783.3 2122.92
  4877.1 2121.71  4916.6 2120.10  4971.7 2116.24  4984.8 2113.71  5001.7 2112.53
  5002.2 2112.03  5008.7 2112.53  5031.2 2113.76  5062.5 2113.20  5093.7 2116.55
  5143.6 2117.76  5184.8 2118.56  5229.2 2120.27  5255.0 2122.14  5288.4 2126.50
  5333.4 2129.15  5568.8 2133.83  5750.3 2140.63  5825.2 2143.77  5870.7 2147.02
#Mann=8,-1,0
  4274.1     0.1       0  4630.6    0.07       0  4984.8     0.1       0
  5001.7    0.05       0  5008.7     0.1       0  5143.6    0.07       0
  5184.8     0.1       0  5750.3    0.07       0
Bank Sta=5001.7,5008.7
Exp/Cntr=0.3,0.1

Chan Stop Cuts=-1