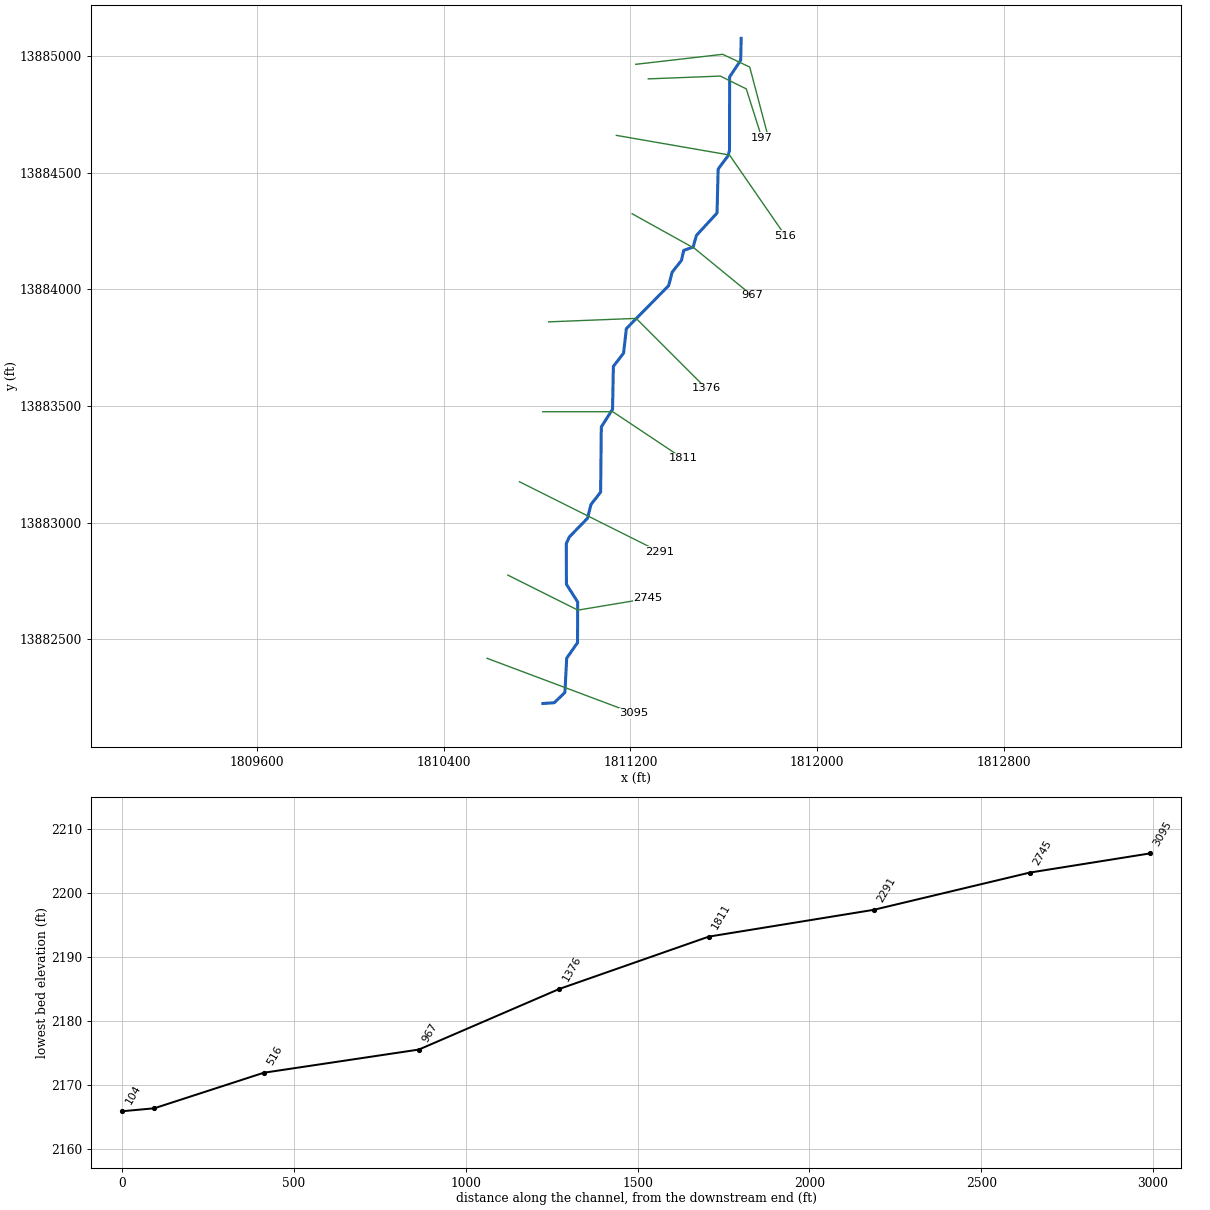
--- Stream0237.prj (project) ---

Proj Title=Stream0237 Base Level Engineering
Current Plan=p01
Default Exp/Contr=0.3,0.1
English Units
Geom File=g01
Flow File=f01
Plan File=p01
BEGIN DESCRIPTION:
Stream0237
END DESCRIPTION:

--- Stream0237.p01 (plan) ---

Plan Title=Multiple Run
Short Identifier=Multiple
Geom File=g01
Flow File=f01
Subcritical Flow
K Sum by GR= 0
Std Step Tol= 0.01
Critical Tol= 0.01
Num of Std Step Trials= 20
Max Error Tol= 0.3
Flow Tol Ratio= 0.001
Split Flow NTrial= 30
Split Flow Tol= 0.02
Split Flow Ratio= 0.02
Log Output Level= 0
Friction Slope Method= 1
Unsteady Friction Slope Method= 2
Unsteady Bridges Friction Slope Method= 1
Parabolic Critical Depth
Global Vel Dist=  1 , 1 , 1
Global Log Level= 0
CheckData=True
Encroach Param= -1, 0, 0, 0
BEGIN DESCRIPTION:
Multiple Run
END DESCRIPTION:

--- Stream0237.f01 (steady flow) ---

Flow Title=Multiple
Number of Profiles=7
Profile Names=10-year,25-year,50-year,1pct_min,100-year,1pct_plu,500-year
River Rch & RM= Stream0237,Reach-1,3095
     693    1152    1578    1047    2088    4167    3611
Boundary for River Rch & Prof#=Stream0237,Reach-1,1
Up Type=0
Dn Type=3
Dn Slope=0.005
Boundary for River Rch & Prof#=Stream0237,Reach-1,2
Up Type=0
Dn Type=3
Dn Slope=0.005
Boundary for River Rch & Prof#=Stream0237,Reach-1,3
Up Type=0
Dn Type=3
Dn Slope=0.005
Boundary for River Rch & Prof#=Stream0237,Reach-1,4
Up Type=0
Dn Type=3
Dn Slope=0.005
Boundary for River Rch & Prof#=Stream0237,Reach-1,5
Up Type=0
Dn Type=3
Dn Slope=0.005
Boundary for River Rch & Prof#=Stream0237,Reach-1,6
Up Type=0
Dn Type=3
Dn Slope=0.005
Boundary for River Rch & Prof#=Stream0237,Reach-1,7
Up Type=0
Dn Type=3
Dn Slope=0.005

--- Stream0237.g01 (geometry) ---

Geom Title=Existing Conditions

River Reach=Stream0237,Reach-1
Reach XY= 30
      1810825.00     13882225.00      1810874.02     13882228.12
      1810919.73     13882272.31      1810927.27     13882419.06
      1810973.78     13882485.51      1810974.48     13882659.78
      1810926.22     13882735.51      1810925.38     13882909.84
      1810938.40     13882938.31      1811016.84     13883018.95
      1811031.14     13883077.17      1811072.76     13883130.93
      1811075.52     13883409.78      1811123.78     13883485.51
      1811127.26     13883669.06      1811171.14     13883726.60
      1811182.86     13883831.17      1811364.24     13884015.32
      1811379.18     13884073.29      1811418.82     13884123.12
      1811428.84     13884166.38      1811469.01     13884180.77
      1811483.25     13884230.76      1811571.45     13884326.47
      1811576.22     13884514.49      1811619.25     13884572.67
      1811624.93     13884595.03      1811625.51     13884909.79
      1811672.90     13884980.87      1811675.00     13885075.00

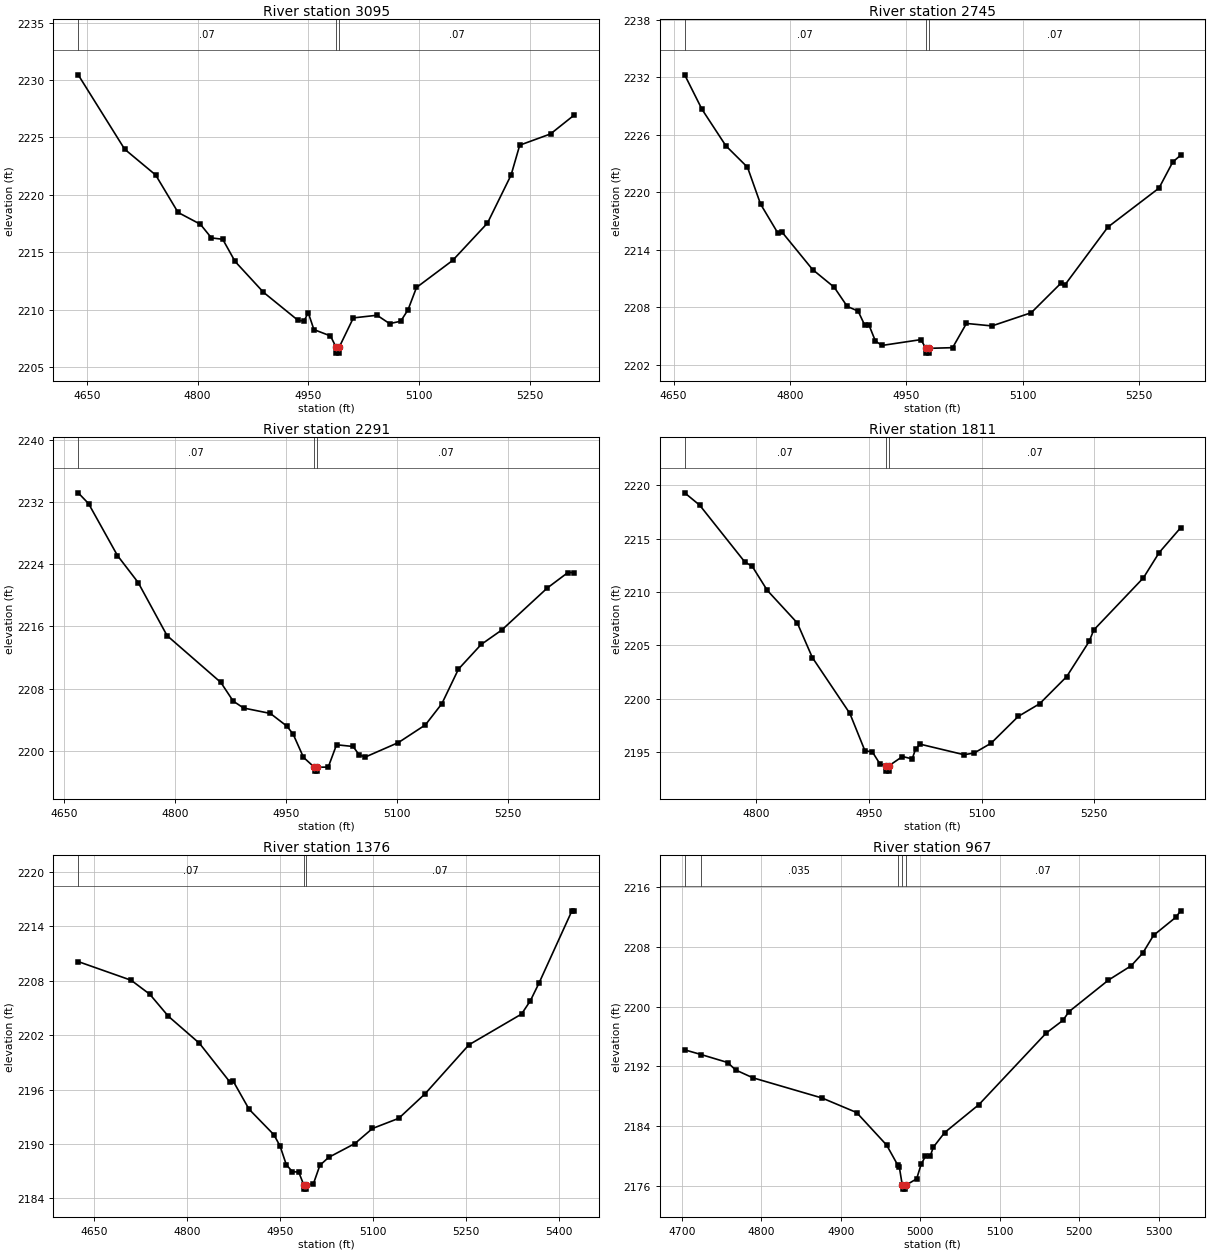
Type RM Length L Ch R = 1,3095,350,350,350
BEGIN DESCRIPTION:
Stream0237 7.0
END DESCRIPTION:
XS GIS Cut Line= 2
      1810586.14     13882418.50      1811214.93     13882182.56
#Sta/Elev= 30
  4638.3 2230.45  4701.2 2223.97  4743.2 2221.72  4773.5 2218.46  4803.7 2217.43
  4818.7 2216.24  4834.0 2216.12  4850.7 2214.19  4889.2 2211.50  4936.1 2209.05
  4944.3 2209.00  4949.7 2209.74  4957.5 2208.25  4979.9 2207.70  4987.6 2206.70
  4987.8 2206.20  4991.3 2206.20  4991.6 2206.70  5010.9 2209.27  5043.0 2209.50
  5060.0 2208.77  5075.0 2208.98  5084.9 2209.97  5096.4 2211.92  5145.4 2214.28
  5192.5 2217.53  5224.5 2221.72  5236.2 2224.32  5277.9 2225.30  5309.9 2226.94
#Mann=3,-1,0
  4638.3    0.07       0  4987.6    0.05       0  4991.6    0.07       0
Bank Sta=4987.6,4991.6
Exp/Cntr=0.3,0.1

Type RM Length L Ch R = 1,2745,454,454,454
BEGIN DESCRIPTION:
Stream0237 6.0
END DESCRIPTION:
XS GIS Cut Line= 3
      1810675.02     13882774.99      1810975.00     13882625.00
      1811274.98     13882675.00
#Sta/Elev= 30
  4664.2 2232.26  4686.5 2228.66  4717.3 2224.85  4745.2 2222.61  4762.0 2218.77
  4784.4 2215.73  4790.0 2215.81  4829.1 2211.93  4857.0 2210.08  4873.8 2208.08
  4887.8 2207.59  4896.2 2206.15  4901.8 2206.14  4910.1 2204.47  4918.5 2204.00
  4968.8 2204.61  4975.2 2203.70  4975.5 2203.20  4979.0 2203.20  4979.2 2203.70
  5009.7 2203.77  5027.5 2206.30  5060.4 2206.04  5111.1 2207.42  5149.1 2210.48
  5154.2 2210.29  5209.9 2216.36  5275.8 2220.43  5293.6 2223.16  5303.7 2223.86
#Mann=3,-1,0
  4664.2    0.07       0  4975.2    0.05       0  4979.2    0.07       0
Bank Sta=4975.2,4979.2
Exp/Cntr=0.3,0.1

Type RM Length L Ch R = 1,2291,480,480,480
BEGIN DESCRIPTION:
Stream0237 5.0
END DESCRIPTION:
XS GIS Cut Line= 3
      1810725.00     13883175.00      1811025.00     13883025.00
      1811324.98     13882875.01
#Sta/Elev= 30
  4668.9 2233.18  4682.9 2231.79  4722.0 2225.11  4750.0 2221.64  4789.1 2214.81
  4861.8 2208.79  4878.5 2206.39  4892.5 2205.50  4928.8 2204.80  4951.2 2203.16
  4959.6 2202.14  4973.6 2199.15  4988.3 2197.88  4988.6 2197.38  4992.1 2197.38
  4992.3 2197.88  5007.1 2197.90  5018.3 2200.77  5040.7 2200.55  5049.0 2199.46
  5057.4 2199.20  5102.1 2201.06  5138.5 2203.33  5160.8 2206.06  5183.2 2210.50
  5213.9 2213.67  5241.9 2215.54  5303.4 2220.94  5331.3 2222.93  5339.7 2222.92
#Mann=3,-1,0
  4668.9    0.07       0  4988.3    0.05       0  4992.3    0.07       0
Bank Sta=4988.3,4992.3
Exp/Cntr=0.3,0.1

Type RM Length L Ch R = 1,1811,435,435,435
BEGIN DESCRIPTION:
Stream0237 4.0
END DESCRIPTION:
XS GIS Cut Line= 3
      1810825.03     13883475.00      1811125.00     13883475.00
      1811424.98     13883275.01
#Sta/Elev= 30
  4704.6 2219.30  4724.6 2218.14  4784.6 2212.82  4794.6 2212.40  4814.6 2210.15
  4854.6 2207.09  4874.6 2203.85  4924.6 2198.60  4944.6 2195.11  4954.6 2194.99
  4964.6 2193.87  4972.6 2193.69  4972.8 2193.19  4976.3 2193.19  4976.6 2193.69
  4994.6 2194.56  5007.6 2194.34  5012.1 2195.25  5018.1 2195.72  5076.7 2194.73
  5090.2 2194.89  5112.7 2195.81  5148.8 2198.32  5177.3 2199.51  5213.4 2202.06
  5243.4 2205.37  5249.4 2206.43  5315.5 2211.32  5336.6 2213.70  5365.1 2216.02
#Mann=3,-1,0
  4704.6    0.07       0  4972.6    0.05       0  4976.6    0.07       0
Bank Sta=4972.6,4976.6
Exp/Cntr=0.3,0.1

Type RM Length L Ch R = 1,1376,409,409,409
BEGIN DESCRIPTION:
Stream0237 3.0
END DESCRIPTION:
XS GIS Cut Line= 3
      1810849.68     13883860.16      1811225.00     13883875.00
      1811525.02     13883574.98
#Sta/Elev= 30
  4624.8 2210.11  4710.2 2208.05  4740.2 2206.51  4770.2 2204.08  4820.3 2201.10
  4869.6 2196.81  4874.6 2196.94  4900.3 2193.83  4940.4 2191.01  4950.4 2189.76
  4960.4 2187.71  4970.4 2186.92  4980.4 2186.90  4988.4 2185.51  4988.7 2185.01
  4992.2 2185.01  4992.4 2185.51  5003.9 2185.55  5014.6 2187.64  5028.7 2188.51
  5071.1 2190.04  5099.4 2191.70  5141.8 2192.82  5184.3 2195.53  5255.0 2200.93
  5339.8 2204.32  5354.0 2205.78  5368.1 2207.75  5421.1 2215.71  5424.7 2215.71
#Mann=3,-1,0
  4624.8    0.07       0  4988.4    0.05       0  4992.4    0.07       0
Bank Sta=4988.4,4992.4
Exp/Cntr=0.3,0.1

Type RM Length L Ch R = 1,967,451,451,451
BEGIN DESCRIPTION:
Stream0237 2.0
END DESCRIPTION:
XS GIS Cut Line= 3
      1811207.79     13884323.21      1811475.00     13884175.00
      1811721.38     13883973.41
#Sta/Elev= 30
  4703.5 2194.21  4724.1 2193.58  4757.5 2192.51  4767.6 2191.51  4789.3 2190.46
  4876.3 2187.75  4919.8 2185.80  4957.6 2181.43  4971.3 2178.80  4973.6 2178.44
  4977.3 2176.03  4977.6 2175.53  4981.1 2175.53  4981.3 2176.03  4995.3 2176.91
  5001.0 2178.86  5006.2 2179.91  5012.3 2179.91  5016.2 2181.14  5030.6 2183.12
  5073.7 2186.87  5158.4 2196.47  5179.2 2198.15  5187.1 2199.34  5236.6 2203.56
  5265.3 2205.49  5279.7 2207.17  5293.3 2209.56  5321.3 2211.98  5327.4 2212.85
#Mann=5,-1,0
  4703.5    0.07       0  4724.1   0.035       0  4971.3    0.07       0
  4977.3    0.05       0  4981.3    0.07       0
Bank Sta=4977.3,4981.3
Exp/Cntr=0.3,0.1

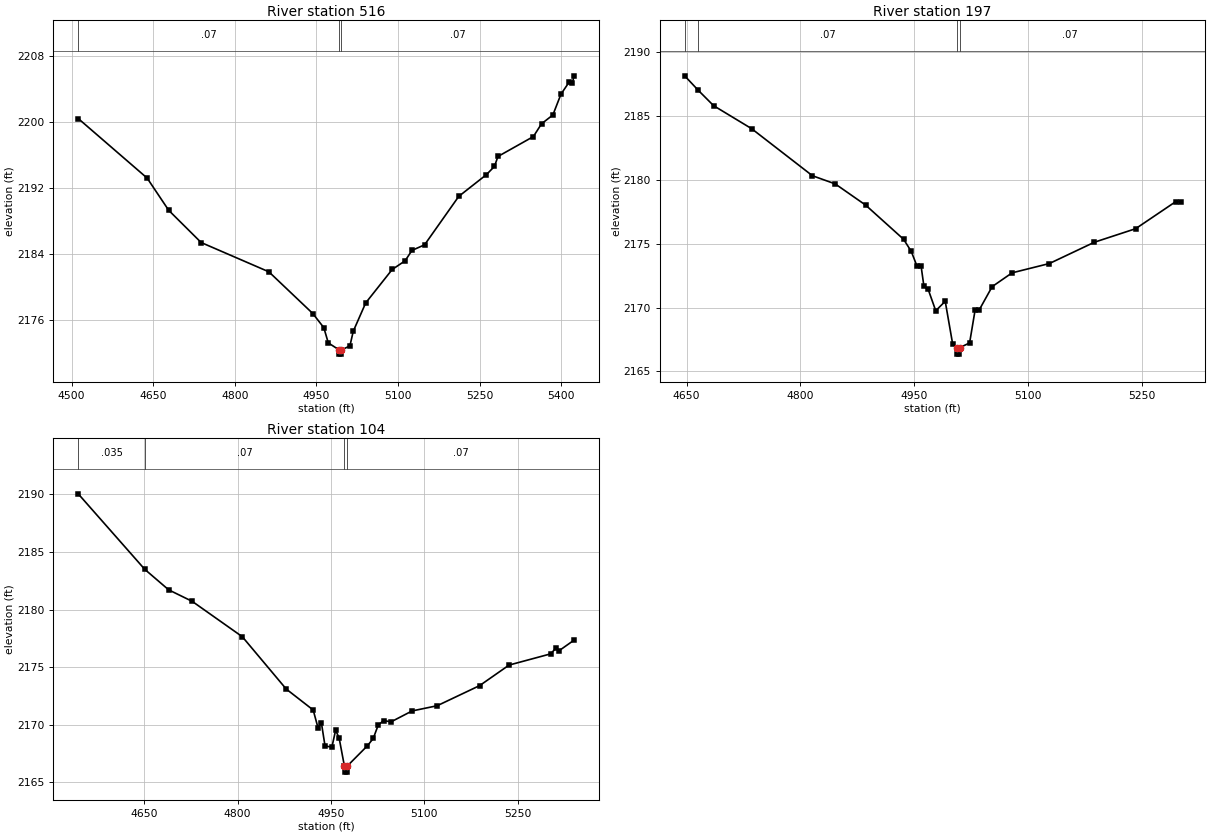
Type RM Length L Ch R = 1,516,319,319,319
BEGIN DESCRIPTION:
Stream0237 1.0
END DESCRIPTION:
XS GIS Cut Line= 3
      1811140.19     13884659.17      1811625.00     13884575.00
      1811863.51     13884229.74
#Sta/Elev= 30
  4512.2 2200.39  4638.9 2193.19  4678.6 2189.29  4738.2 2185.40  4862.7 2181.86
  4943.4 2176.82  4963.7 2175.11  4971.9 2173.27  4992.1 2172.41  4992.4 2171.91
  4995.9 2171.91  4996.1 2172.41  5011.7 2172.91  5017.8 2174.67  5040.7 2178.10
  5089.4 2182.14  5113.1 2183.19  5125.8 2184.45  5148.9 2185.12  5211.8 2190.98
  5262.5 2193.60  5277.4 2194.60  5283.8 2195.80  5349.0 2198.21  5363.9 2199.75
  5384.8 2200.82  5399.7 2203.34  5414.6 2204.78  5420.7 2204.73  5423.9 2205.55
#Mann=3,-1,0
  4512.2    0.07       0  4992.1    0.05       0  4996.1    0.07       0
Bank Sta=4992.1,4996.1
Exp/Cntr=0.3,0.1

Type RM Length L Ch R = 1,197,93,93,93
BEGIN DESCRIPTION:
Stream0237 0.0
END DESCRIPTION:
XS GIS Cut Line= 4
      1811276.97     13884901.27      1811585.49     13884913.29
      1811696.73     13884858.40      1811763.29     13884648.61
#Sta/Elev= 30
  4647.6 2188.16  4665.4 2187.03  4685.7 2185.82  4735.7 2184.02  4815.8 2180.33
  4845.8 2179.69  4885.8 2178.03  4935.8 2175.35  4945.9 2174.40  4953.6 2173.22
  4958.9 2173.22  4962.6 2171.65  4968.2 2171.42  4978.1 2169.75  4990.6 2170.49
  5000.4 2167.14  5005.5 2166.85  5005.7 2166.35  5009.2 2166.35  5009.5 2166.85
  5022.7 2167.23  5029.9 2169.79  5035.5 2169.83  5052.4 2171.64  5078.6 2172.72
  5127.7 2173.45  5187.0 2175.12  5241.3 2176.18  5294.3 2178.31  5300.5 2178.30
#Mann=4,-1,0
  4647.6   0.035       0  4665.4    0.07       0  5005.5    0.05       0
  5009.5    0.07       0
Bank Sta=5005.5,5009.5
Exp/Cntr=0.3,0.1

Type RM Length L Ch R = 1,104,0,0,0
BEGIN DESCRIPTION:
Strean0237 0.1
END DESCRIPTION:
XS GIS Cut Line= 4
      1811223.24     13884963.65      1811595.62     13885006.61
      1811711.51     13884951.93      1811786.60     13884668.39
#Sta/Elev= 30
  4544.1 2190.04  4650.9 2183.49  4689.3 2181.71  4727.1 2180.71  4807.6 2177.64
  4878.1 2173.10  4921.4 2171.28  4929.1 2169.74  4934.6 2170.15  4940.4 2168.16
  4951.4 2168.06  4957.4 2169.52  4963.0 2168.86  4971.6 2166.39  4971.8 2165.89
  4975.3 2165.89  4975.6 2166.39  5008.5 2168.18  5017.8 2168.81  5025.7 2169.96
  5034.4 2170.37  5046.3 2170.25  5080.2 2171.20  5120.4 2171.65  5188.7 2173.40
  5235.9 2175.18  5302.5 2176.15  5311.2 2176.65  5316.3 2176.43  5340.4 2177.35
#Mann=4,-1,0
  4544.1   0.035       0  4650.9    0.07       0  4971.6    0.05       0
  4975.6    0.07       0
Bank Sta=4971.6,4975.6
Exp/Cntr=0.3,0.1

Chan Stop Cuts=-1