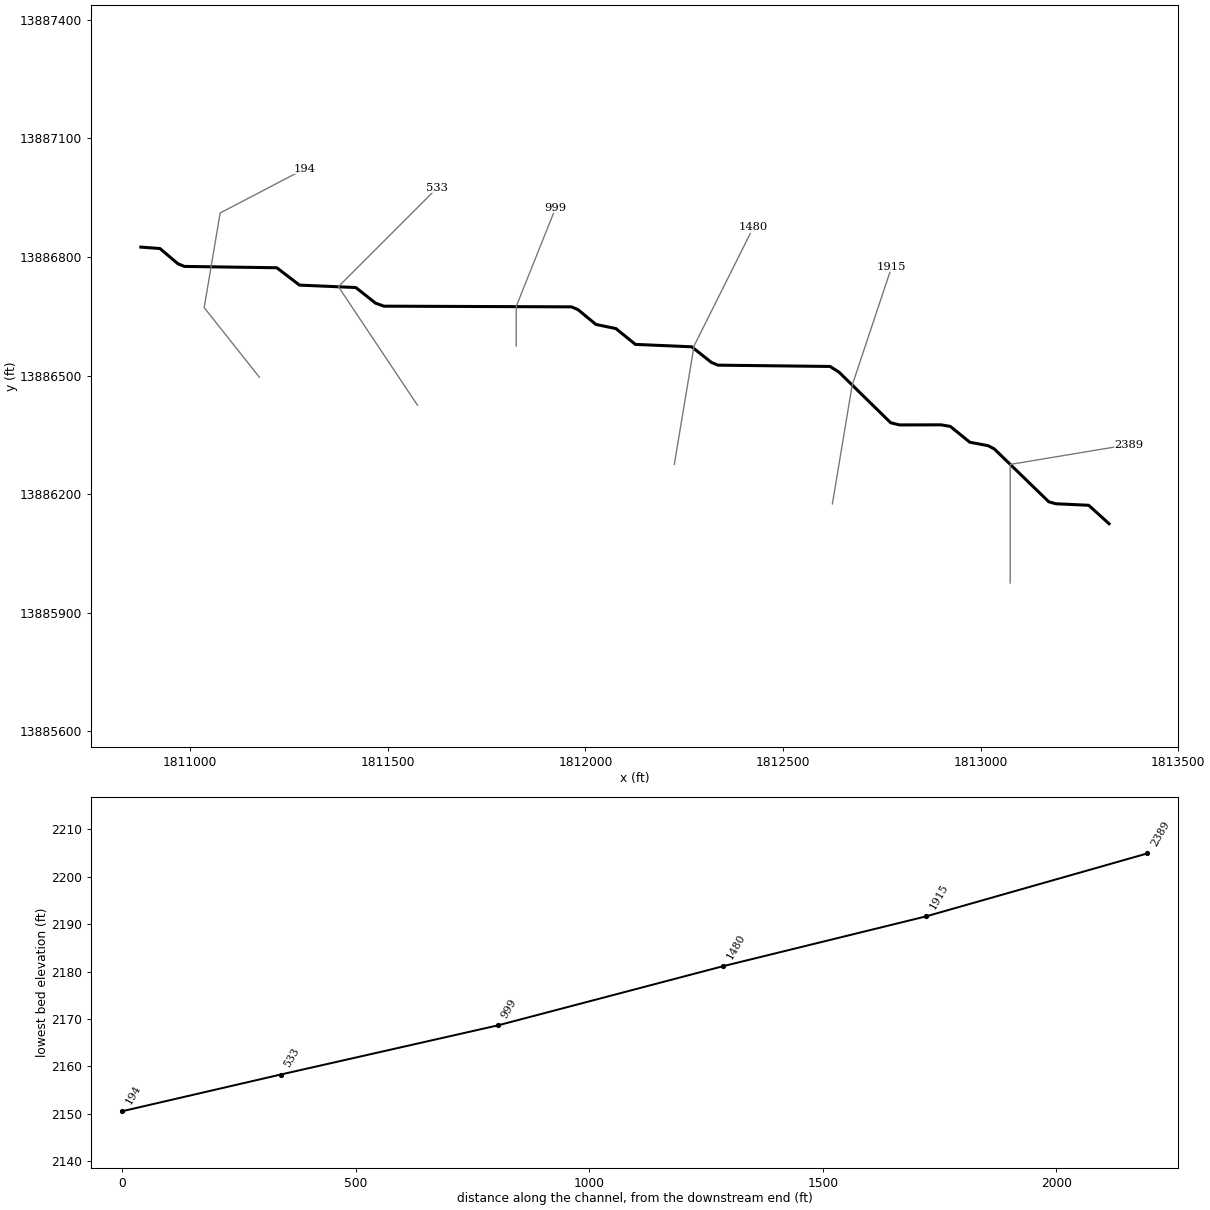
--- Stream0238.prj (project) ---

Proj Title=Stream0238 Base Level Engineering
Current Plan=p01
Default Exp/Contr=0.3,0.1
English Units
Geom File=g01
Flow File=f01
Plan File=p01
BEGIN DESCRIPTION:
Stream0238
END DESCRIPTION:

--- Stream0238.p01 (plan) ---

Plan Title=Multiple Run
Short Identifier=Multiple
Geom File=g01
Flow File=f01
Subcritical Flow
K Sum by GR= 0
Std Step Tol= 0.01
Critical Tol= 0.01
Num of Std Step Trials= 20
Max Error Tol= 0.3
Flow Tol Ratio= 0.001
Split Flow NTrial= 30
Split Flow Tol= 0.02
Split Flow Ratio= 0.02
Log Output Level= 0
Friction Slope Method= 1
Unsteady Friction Slope Method= 2
Unsteady Bridges Friction Slope Method= 1
Parabolic Critical Depth
Global Vel Dist=  1 , 1 , 1
Global Log Level= 0
CheckData=True
Encroach Param= -1, 0, 0, 0
BEGIN DESCRIPTION:
Multiple Run
END DESCRIPTION:

--- Stream0238.f01 (steady flow) ---

Flow Title=Multiple
Number of Profiles=7
Profile Names=10-year,25-year,50-year,1pct_min,100-year,1pct_plu,500-year
River Rch & RM= Stream0238,Reach-1,2389
     306     483     639     411     821    1637    1331
Boundary for River Rch & Prof#=Stream0238,Reach-1,1
Up Type=0
Dn Type=3
Dn Slope=0.005
Boundary for River Rch & Prof#=Stream0238,Reach-1,2
Up Type=0
Dn Type=3
Dn Slope=0.005
Boundary for River Rch & Prof#=Stream0238,Reach-1,3
Up Type=0
Dn Type=3
Dn Slope=0.005
Boundary for River Rch & Prof#=Stream0238,Reach-1,4
Up Type=0
Dn Type=3
Dn Slope=0.005
Boundary for River Rch & Prof#=Stream0238,Reach-1,5
Up Type=0
Dn Type=3
Dn Slope=0.005
Boundary for River Rch & Prof#=Stream0238,Reach-1,6
Up Type=0
Dn Type=3
Dn Slope=0.005
Boundary for River Rch & Prof#=Stream0238,Reach-1,7
Up Type=0
Dn Type=3
Dn Slope=0.005

--- Stream0238.g01 (geometry) ---

Geom Title=Existing Conditions

River Reach=Stream0238,Reach-1
Reach XY= 30
      1813325.00     13886125.00      1813273.59     13886171.61
      1813190.19     13886175.47      1813172.56     13886180.50
      1813034.68     13886314.24      1813018.97     13886322.50
      1812972.83     13886331.14      1812923.44     13886371.24
      1812900.08     13886375.19      1812794.99     13886374.98
      1812772.55     13886380.47      1812641.76     13886508.57
      1812619.15     13886522.94      1812335.50     13886526.22
      1812318.94     13886533.14      1812269.06     13886572.73
      1812126.56     13886578.76      1812077.18     13886618.88
      1812026.74     13886629.19      1811981.08     13886666.91
      1811964.50     13886673.80      1811490.22     13886675.52
      1811468.94     13886683.14      1811419.06     13886722.73
      1811276.57     13886728.79      1811219.06     13886772.74
      1810985.46     13886776.12      1810968.84     13886782.89
      1810923.49     13886821.35      1810875.00     13886825.00

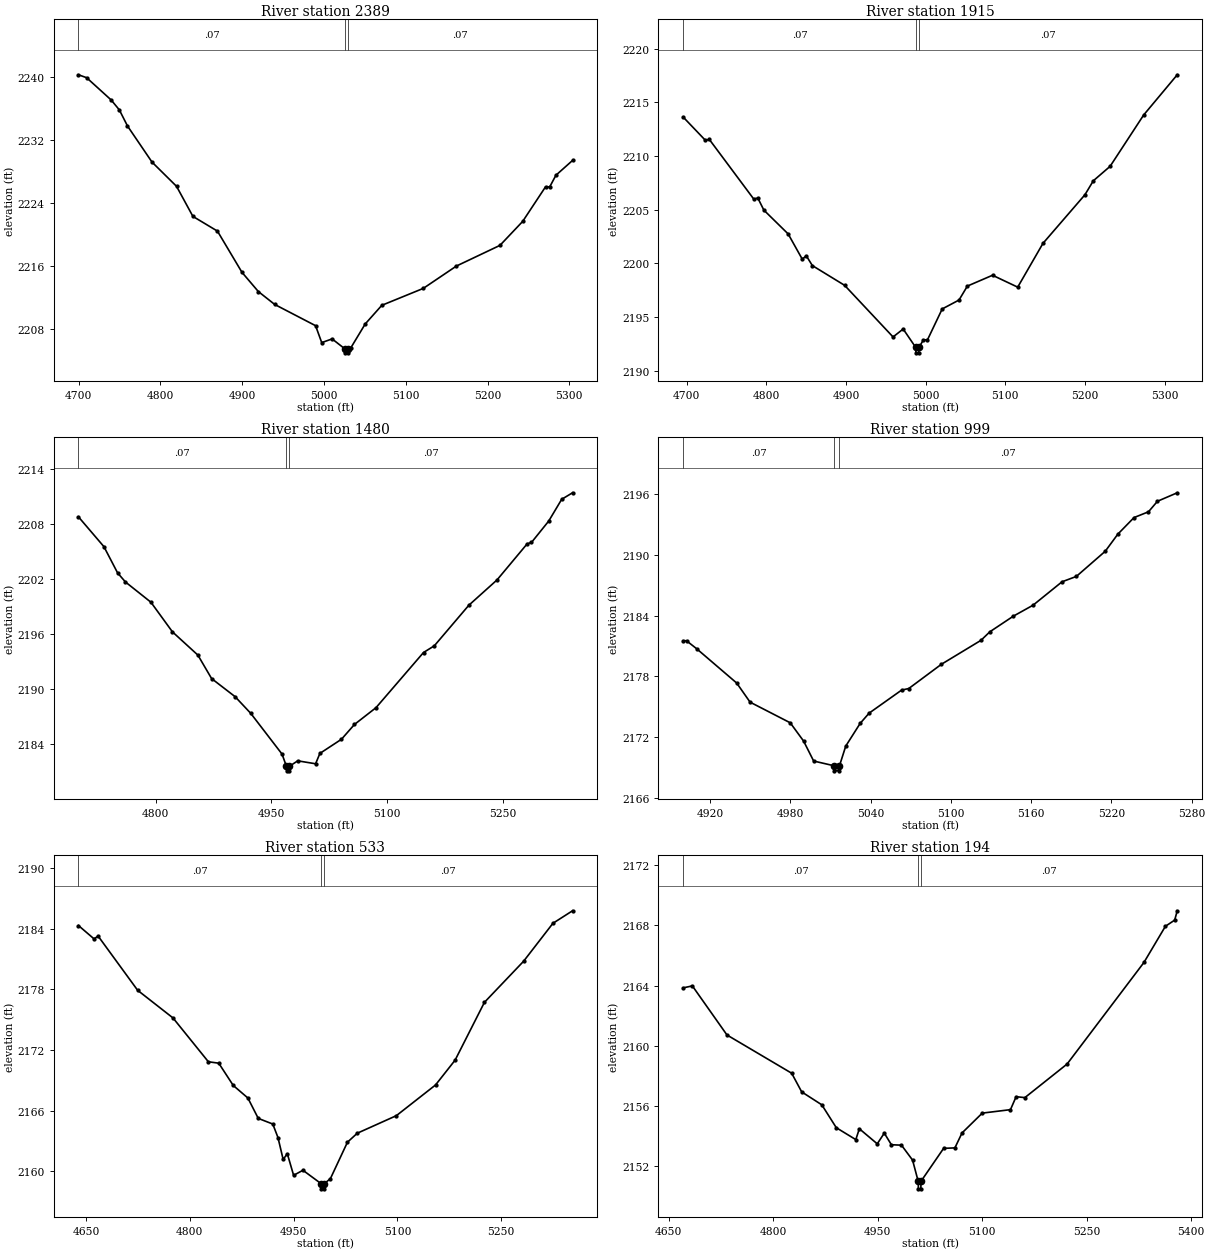
Type RM Length L Ch R = 1,2389,474,474,474
BEGIN DESCRIPTION:
Stream0238 5.0
END DESCRIPTION:
XS GIS Cut Line= 3
      1813075.00     13885974.96      1813075.00     13886275.00
      1813375.03     13886325.00
#Sta/Elev= 30
  4699.7 2240.29  4709.7 2239.92  4739.7 2237.09  4749.7 2235.83  4759.7 2233.78
  4789.7 2229.19  4819.7 2226.11  4839.7 2222.29  4869.7 2220.42  4899.7 2215.18
  4919.7 2212.74  4939.7 2211.10  4989.7 2208.40  4997.2 2206.25  5009.9 2206.72
  5025.6 2205.45  5025.9 2204.95  5029.4 2204.95  5029.6 2205.45  5032.7 2205.57
  5050.4 2208.62  5070.7 2210.99  5121.4 2213.14  5161.9 2215.98  5215.2 2218.61
  5243.0 2221.66  5270.9 2226.05  5276.0 2226.04  5283.6 2227.52  5303.9 2229.40
#Mann=3,-1,0
  4699.7    0.07       0  5025.6    0.05       0  5029.6    0.07       0
Bank Sta=5025.6,5029.6
Exp/Cntr=0.3,0.1

Type RM Length L Ch R = 1,1915,435,435,435
BEGIN DESCRIPTION:
Stream0238 4.0
END DESCRIPTION:
XS GIS Cut Line= 3
      1812625.01     13886175.04      1812675.00     13886475.00
      1812774.99     13886774.98
#Sta/Elev= 30
  4695.6 2213.62  4723.4 2211.46  4728.5 2211.53  4784.3 2205.97  4789.3 2206.08
  4796.9 2204.95  4827.4 2202.73  4845.1 2200.38  4850.2 2200.69  4857.8 2199.78
  4898.3 2197.94  4959.1 2193.13  4971.8 2193.87  4987.6 2192.15  4987.8 2191.65
  4991.3 2191.65  4991.6 2192.15  4997.2 2192.86  5002.3 2192.86  5020.8 2195.74
  5041.9 2196.57  5052.4 2197.87  5084.0 2198.88  5115.6 2197.77  5147.3 2201.85
  5200.0 2206.38  5210.5 2207.68  5231.6 2209.03  5273.8 2213.82  5315.9 2217.56
#Mann=3,-1,0
  4695.6    0.07       0  4987.6    0.05       0  4991.6    0.07       0
Bank Sta=4987.6,4991.6
Exp/Cntr=0.3,0.1

Type RM Length L Ch R = 1,1480,481,481,481
BEGIN DESCRIPTION:
Stream0238 3.0
END DESCRIPTION:
XS GIS Cut Line= 3
      1812224.99     13886274.96      1812275.00     13886575.00
      1812425.00     13886875.01
#Sta/Elev= 30
  4700.1 2208.79  4733.1 2205.54  4750.8 2202.68  4761.0 2201.69  4793.9 2199.49
  4821.8 2196.26  4854.7 2193.73  4872.5 2191.17  4902.9 2189.20  4923.2 2187.38
  4963.7 2182.94  4969.3 2181.62  4969.6 2181.12  4973.1 2181.12  4973.3 2181.62
  4984.0 2182.21  5007.1 2181.89  5012.7 2183.02  5040.6 2184.56  5057.4 2186.17
  5085.3 2188.00  5146.8 2194.01  5160.8 2194.74  5205.5 2199.16  5241.9 2201.91
  5281.0 2205.85  5286.6 2206.00  5308.9 2208.33  5325.7 2210.70  5339.7 2211.41
#Mann=3,-1,0
  4700.1    0.07       0  4969.3    0.05       0  4973.3    0.07       0
Bank Sta=4969.3,4973.3
Exp/Cntr=0.3,0.1

Type RM Length L Ch R = 1,999,466,466,466
BEGIN DESCRIPTION:
Stream0238 2.0
END DESCRIPTION:
XS GIS Cut Line= 3
      1811825.00     13886575.04      1811825.00     13886675.00
      1811924.99     13886924.98
#Sta/Elev= 30
  4900.0 2181.51  4902.5 2181.51  4910.0 2180.73  4940.0 2177.33  4950.0 2175.44
  4980.0 2173.40  4990.0 2171.59  4997.5 2169.62  5012.8 2169.15  5013.0 2168.65
  5016.5 2168.65  5016.8 2169.15  5021.5 2171.10  5032.3 2173.35  5039.0 2174.36
  5063.2 2176.63  5068.6 2176.79  5092.9 2179.18  5122.5 2181.55  5129.2 2182.40
  5146.7 2183.94  5161.5 2185.03  5183.1 2187.34  5193.8 2187.87  5215.4 2190.36
  5224.8 2192.05  5236.9 2193.69  5247.7 2194.26  5254.4 2195.30  5269.2 2196.14
#Mann=3,-1,0
  4900.0    0.07       0  5012.8    0.05       0  5016.8    0.07       0
Bank Sta=5012.8,5016.8
Exp/Cntr=0.3,0.1

Type RM Length L Ch R = 1,533,339,339,339
BEGIN DESCRIPTION:
Stream0238 1.0
END DESCRIPTION:
XS GIS Cut Line= 3
      1811574.99     13886425.02      1811375.00     13886725.00
      1811625.01     13886975.01
#Sta/Elev= 30
  4639.0 2184.33  4661.5 2183.01  4667.5 2183.28  4724.6 2177.91  4775.7 2175.17
  4826.8 2170.83  4841.8 2170.69  4862.8 2168.48  4883.9 2167.24  4898.9 2165.22
  4919.9 2164.66  4927.4 2163.32  4934.9 2161.15  4940.9 2161.72  4950.0 2159.58
  4963.5 2160.08  4990.0 2158.74  4990.3 2158.24  4993.8 2158.24  4994.0 2158.74
  5003.1 2159.24  5027.8 2162.86  5042.0 2163.75  5098.5 2165.49  5155.1 2168.53
  5183.4 2170.99  5225.8 2176.72  5282.4 2180.79  5324.8 2184.55  5353.1 2185.79
#Mann=3,-1,0
  4639.0    0.07       0  4990.0    0.05       0  4994.0    0.07       0
Bank Sta=4990,4994
Exp/Cntr=0.3,0.1

Type RM Length L Ch R = 1,194,0,0,0
BEGIN DESCRIPTION:
Stream0238 0.0
END DESCRIPTION:
XS GIS Cut Line= 4
      1811175.01     13886495.69      1811035.37     13886671.83
      1811075.72     13886911.28      1811290.09     13887023.35
#Sta/Elev= 30
  4670.8 2163.85  4684.0 2163.98  4733.7 2160.72  4826.6 2158.18  4841.0 2156.94
  4869.9 2156.08  4890.7 2154.56  4918.7 2153.77  4923.8 2154.49  4949.5 2153.49
  4959.6 2154.20  4969.8 2153.43  4984.3 2153.40  5000.2 2152.41  5008.3 2151.00
  5008.6 2150.50  5012.1 2150.50  5012.3 2151.00  5044.8 2153.19  5061.0 2153.22
  5071.2 2154.21  5100.3 2155.53  5140.8 2155.76  5148.9 2156.62  5161.5 2156.56
  5222.1 2158.79  5332.5 2165.54  5363.3 2167.94  5376.6 2168.35  5380.3 2168.97
#Mann=3,-1,0
  4670.8    0.07       0  5008.3    0.05       0  5012.3    0.07       0
Bank Sta=5008.3,5012.3
Exp/Cntr=0.3,0.1

Chan Stop Cuts=-1