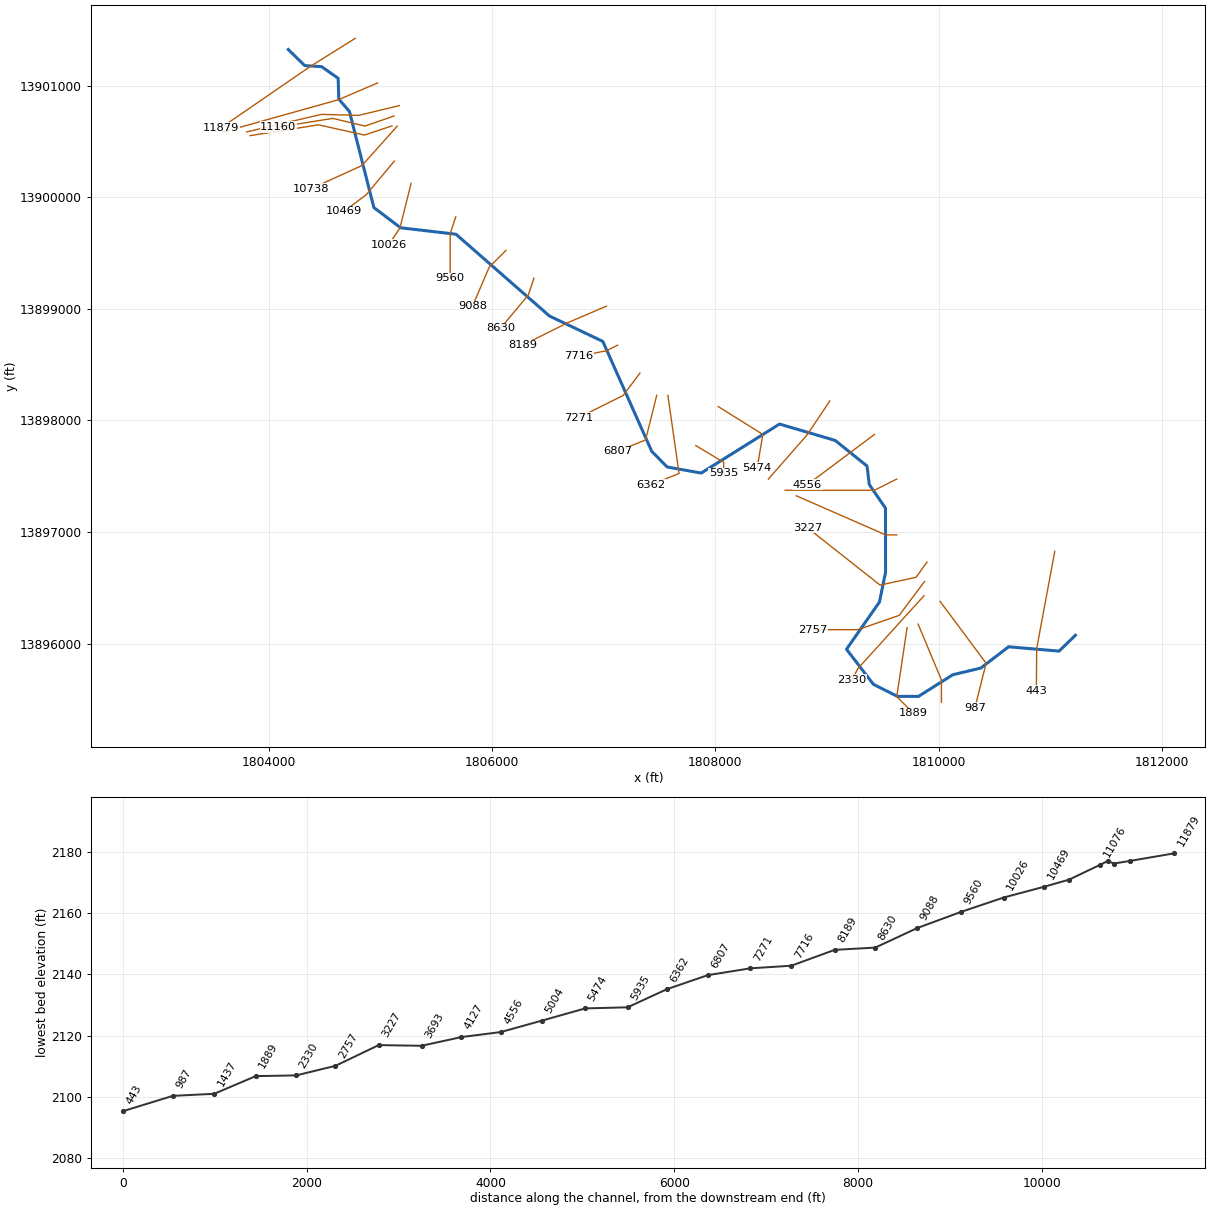
--- Stream0241.prj (project) ---

Proj Title=Stream0241 Base Level Engineering
Current Plan=p01
Default Exp/Contr=0.3,0.1
English Units
Geom File=g01
Flow File=f01
Plan File=p01
BEGIN DESCRIPTION:
Stream0241
END DESCRIPTION:

--- Stream0241.p01 (plan) ---

Plan Title=Multiple Run
Short Identifier=Multiple
Geom File=g01
Flow File=f01
Subcritical Flow
K Sum by GR= 0
Std Step Tol= 0.01
Critical Tol= 0.01
Num of Std Step Trials= 20
Max Error Tol= 0.3
Flow Tol Ratio= 0.001
Split Flow NTrial= 30
Split Flow Tol= 0.02
Split Flow Ratio= 0.02
Log Output Level= 0
Friction Slope Method= 1
Unsteady Friction Slope Method= 2
Unsteady Bridges Friction Slope Method= 1
Parabolic Critical Depth
Global Vel Dist=  1 , 1 , 1
Global Log Level= 0
CheckData=True
Encroach Param= -1, 0, 0, 0
BEGIN DESCRIPTION:
Multiple Run
END DESCRIPTION:

--- Stream0241.f01 (steady flow) ---

Flow Title=Multiple
Number of Profiles=7
Profile Names=10-year,25-year,50-year,1pct_min,100-year,1pct_plu,500-year
River Rch & RM= Stream0241,Reach-1,11879
    1584    2750    3875    2633    5254   10483    9560
River Rch & RM= Stream0241,Reach-1,5004
    2007    3540    5039    3455    6894   13756   12785
River Rch & RM= Stream0241,Reach-1,2330
    2501    4457    6390    4409    8798   17553   16523
River Rch & RM= Stream0241,Reach-1,443
    2864    5135    7393    5121   10217   20386   19337
Boundary for River Rch & Prof#=Stream0241,Reach-1,1
Up Type=0
Dn Type=3
Dn Slope=0.005
Boundary for River Rch & Prof#=Stream0241,Reach-1,2
Up Type=0
Dn Type=3
Dn Slope=0.005
Boundary for River Rch & Prof#=Stream0241,Reach-1,3
Up Type=0
Dn Type=3
Dn Slope=0.005
Boundary for River Rch & Prof#=Stream0241,Reach-1,4
Up Type=0
Dn Type=3
Dn Slope=0.005
Boundary for River Rch & Prof#=Stream0241,Reach-1,5
Up Type=0
Dn Type=3
Dn Slope=0.005
Boundary for River Rch & Prof#=Stream0241,Reach-1,6
Up Type=0
Dn Type=3
Dn Slope=0.005
Boundary for River Rch & Prof#=Stream0241,Reach-1,7
Up Type=0
Dn Type=3
Dn Slope=0.005

--- Stream0241.g01 (geometry) ---

Geom Title=Existing Conditions

River Reach=Stream0241,Reach-1
Reach XY= 30
      1804175.00     13901325.00      1804322.55     13901180.46
      1804473.53     13901171.45      1804621.93     13901066.70
      1804627.07     13900880.86      1804722.93     13900769.14
      1804941.64     13899908.32      1805180.93     13899727.24
      1805677.30     13899669.17      1806515.32     13898935.76
      1806992.13     13898708.70      1807430.83     13897722.70
      1807568.94     13897583.14      1807873.45     13897528.75
      1808574.86     13897968.09      1809073.42     13897821.18
      1809358.57     13897591.76      1809378.55     13897426.47
      1809523.80     13897214.50      1809524.48     13896640.22
      1809469.54     13896372.55      1809174.72     13895949.68
      1809415.32     13895635.76      1809630.93     13895527.24
      1809819.14     13895527.06      1810126.56     13895721.24
      1810377.29     13895780.84      1810626.36     13895971.71
      1811078.34     13895932.98      1811225.00     13896075.00

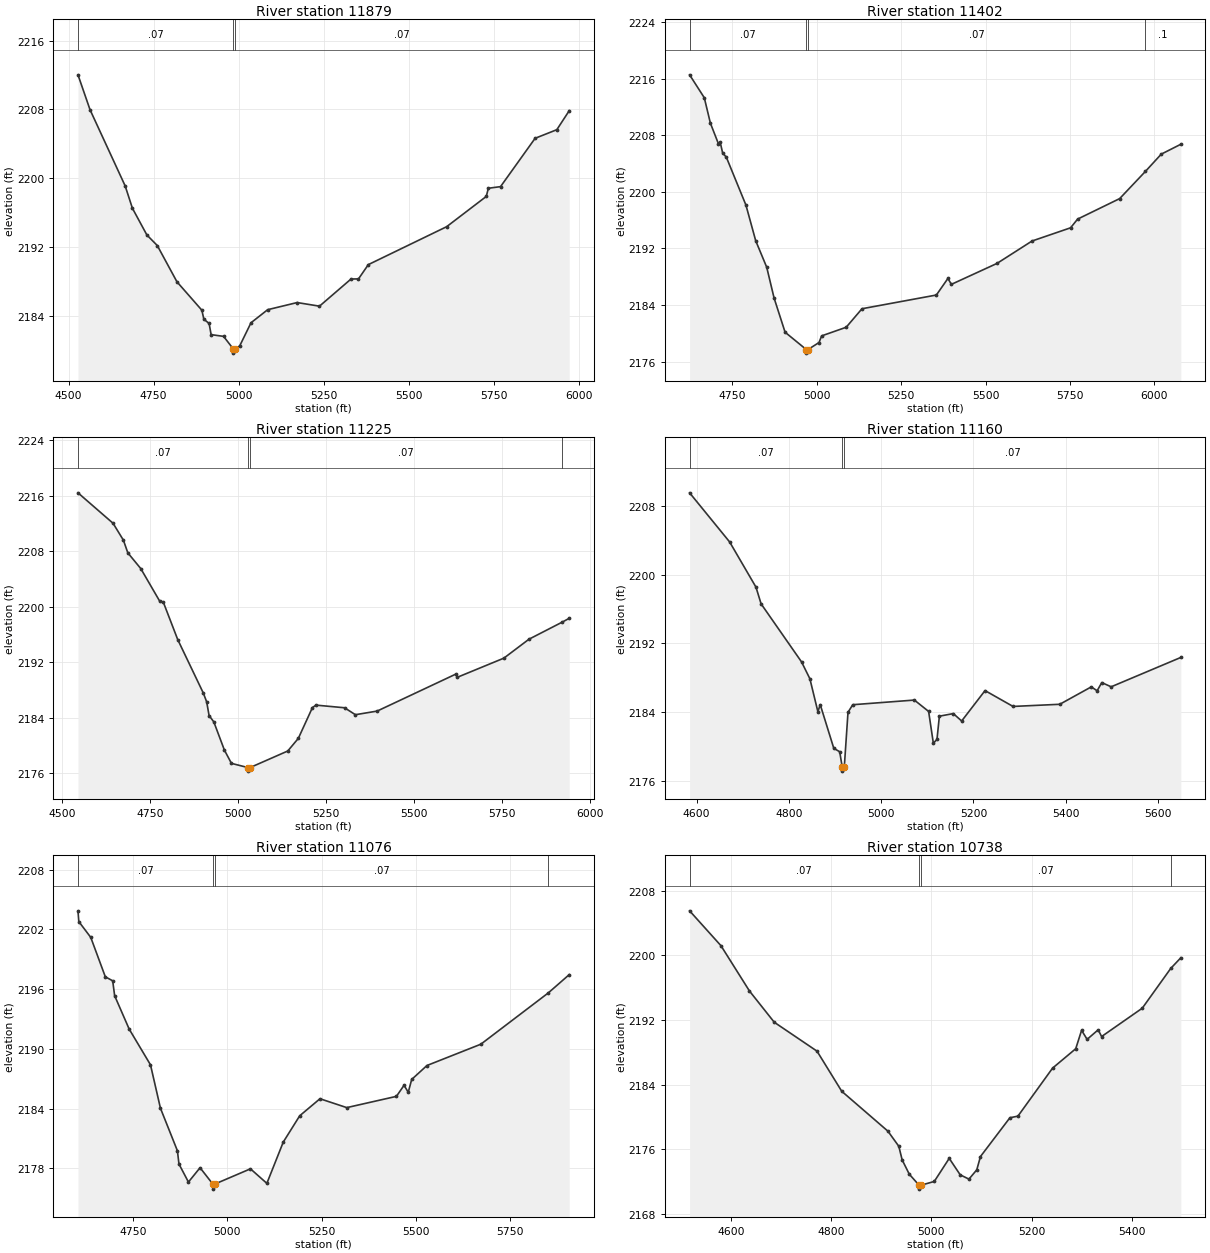
Type RM Length L Ch R = 1,11879,477,477,477
BEGIN DESCRIPTION:
Stream0241 26.0
END DESCRIPTION:
XS GIS Cut Line= 3
      1804775.03     13901425.02      1804375.00     13901175.00
      1803574.97     13900624.98
#Sta/Elev= 30
  4527.7 2212.01  4563.1 2207.95  4666.3 2199.09  4687.5 2196.50  4730.0 2193.39
  4760.6 2192.16  4818.4 2187.94  4891.5 2184.64  4897.4 2183.59  4912.8 2183.10
  4918.7 2181.80  4955.2 2181.60  4983.6 2180.15  4983.9 2179.65  4988.1 2180.15
  5002.5 2180.48  5035.8 2183.18  5084.7 2184.70  5171.3 2185.53  5236.9 2185.11
  5329.6 2188.27  5351.4 2188.28  5380.3 2189.94  5610.3 2194.35  5726.7 2197.87
  5732.8 2198.82  5768.6 2199.01  5870.1 2204.63  5933.9 2205.63  5970.3 2207.84
#Mann=3,-1,0
  4527.7    0.07       0  4983.6    0.05       0  4988.1    0.07       0
Bank Sta=4983.6,4988.1
Exp/Cntr=0.3,0.1

Type RM Length L Ch R = 1,11402,177,177,177
BEGIN DESCRIPTION:
Stream0241 25.0
END DESCRIPTION:
XS GIS Cut Line= 3
      1804974.96     13901024.98      1804625.00     13900875.00
      1803590.53     13900585.36
#Sta/Elev= 30
  4623.1 2216.56  4666.6 2213.32  4684.7 2209.72  4708.3 2206.83  4713.7 2207.03
  4721.0 2205.50  4731.9 2204.91  4789.9 2198.14  4818.9 2193.09  4851.5 2189.34
  4873.3 2184.99  4905.9 2180.15  4968.9 2177.69  4969.3 2177.19  4973.5 2177.69
  5006.4 2178.69  5014.2 2179.63  5086.9 2180.85  5133.7 2183.47  5354.0 2185.41
  5388.1 2187.75  5398.5 2186.92  5533.5 2189.88  5637.3 2193.05  5751.5 2194.92
  5772.3 2196.15  5896.9 2199.05  5973.2 2202.90  6020.1 2205.34  6078.1 2206.74
#Mann=4,-1,0
  4623.1    0.07       0  4968.9    0.05       0  4973.5    0.07       0
  5973.2     0.1       0
Bank Sta=4968.9,4973.5
Exp/Cntr=0.3,0.1

Type RM Length L Ch R = 1,11225,65,65,65
BEGIN DESCRIPTION:
Stream0241 24.3
END DESCRIPTION:
XS GIS Cut Line= 4
      1805170.42     13900822.52      1804806.80     13900734.79
      1804471.27     13900743.43      1803803.77     13900586.49
#Sta/Elev= 30
  4544.6 2216.43  4644.3 2212.04  4673.6 2209.61  4686.2 2207.78  4722.9 2205.52
  4776.5 2200.84  4786.8 2200.70  4827.9 2195.29  4900.8 2187.56  4910.2 2186.30
  4917.0 2184.34  4930.5 2183.42  4960.5 2179.36  4980.5 2177.45  5028.2 2176.83
  5028.5 2176.33  5032.8 2176.83  5140.5 2179.23  5170.5 2181.05  5210.6 2185.49
  5220.6 2185.84  5301.8 2185.46  5332.6 2184.46  5394.3 2184.98  5617.0 2190.29
  5622.1 2189.85  5754.4 2192.61  5825.7 2195.34  5920.5 2197.81  5940.0 2198.35
#Mann=4,-1,0
  4544.6    0.07       0  5028.2    0.05       0  5032.8    0.07       0
  5920.5     0.1       0
Bank Sta=5028.2,5032.8
Exp/Cntr=0.3,0.1

Type RM Length L Ch R = 1,11160,84,84,84
BEGIN DESCRIPTION:
Stream0241 24.2
END DESCRIPTION:
XS GIS Cut Line= 4
      1805121.47     13900728.63      1804861.92     13900638.86
      1804572.89     13900707.55      1804085.78     13900629.79
#Sta/Elev= 30
  4584.7 2209.49  4671.6 2203.78  4728.6 2198.54  4739.7 2196.60  4827.4 2189.86
  4845.5 2187.90  4862.8 2184.08  4867.9 2184.90  4897.3 2179.83  4910.1 2179.43
  4915.5 2177.68  4915.9 2177.18  4920.1 2177.68  4928.1 2184.01  4938.4 2184.89
  5072.0 2185.43  5102.9 2184.11  5113.1 2180.43  5121.0 2180.86  5126.2 2183.56
  5156.4 2183.86  5174.5 2183.00  5225.2 2186.53  5285.9 2184.69  5387.2 2184.94
  5455.5 2186.96  5468.2 2186.51  5478.3 2187.46  5498.6 2186.97  5649.7 2190.38
#Mann=3,-1,0
  4584.7    0.07       0  4915.5    0.05       0  4920.1    0.07       0
Bank Sta=4915.5,4920.1
Exp/Cntr=0.3,0.1

Type RM Length L Ch R = 1,11076,338,338,338
BEGIN DESCRIPTION:
Stream0241 24.1
END DESCRIPTION:
XS GIS Cut Line= 4
      1805103.81     13900640.14      1804857.14     13900558.21
      1804445.76     13900649.67      1803832.51     13900552.82
#Sta/Elev= 30
  4604.4 2203.87  4606.6 2202.79  4638.3 2201.20  4676.9 2197.24  4696.4 2196.84
  4701.6 2195.34  4740.1 2191.99  4796.6 2188.40  4823.0 2184.04  4868.0 2179.76
  4872.1 2178.43  4897.2 2176.62  4928.0 2178.06  4962.0 2176.41  4962.3 2175.91
  4966.6 2176.41  5061.6 2177.95  5105.1 2176.49  5148.6 2180.64  5192.2 2183.28
  5245.9 2184.99  5316.9 2184.10  5448.5 2185.23  5468.7 2186.34  5479.9 2185.64
  5489.0 2186.93  5529.5 2188.33  5672.3 2190.47  5851.0 2195.62  5906.6 2197.46
#Mann=4,-1,0
  4604.4    0.07       0  4962.0    0.05       0  4966.6    0.07       0
  5851.0     0.1       0
Bank Sta=4962,4966.6
Exp/Cntr=0.3,0.1

Type RM Length L Ch R = 1,10738,269,269,269
BEGIN DESCRIPTION:
Stream0241 24.0
END DESCRIPTION:
XS GIS Cut Line= 3
      1805150.59     13900637.77      1804835.17     13900285.03
      1804375.03     13900075.01
#Sta/Elev= 30
  4518.1 2205.52  4580.6 2201.20  4637.4 2195.59  4686.8 2191.72  4772.0 2188.14
  4821.3 2183.17  4913.3 2178.23  4935.0 2176.36  4941.7 2174.67  4955.9 2172.90
  4975.2 2171.55  4975.6 2171.05  4980.1 2171.55  5005.7 2172.00  5035.5 2174.86
  5057.4 2172.82  5074.8 2172.29  5090.4 2173.44  5097.8 2175.09  5156.4 2179.89
  5172.4 2180.09  5241.5 2186.04  5287.6 2188.44  5299.3 2190.72  5310.3 2189.60
  5332.3 2190.78  5339.2 2189.95  5420.2 2193.46  5477.0 2198.39  5497.1 2199.71
#Mann=4,-1,0
  4518.1    0.07       0  4975.2    0.05       0  4980.1    0.07       0
  5477.0     0.1       0
Bank Sta=4975.2,4980.1
Exp/Cntr=0.3,0.1

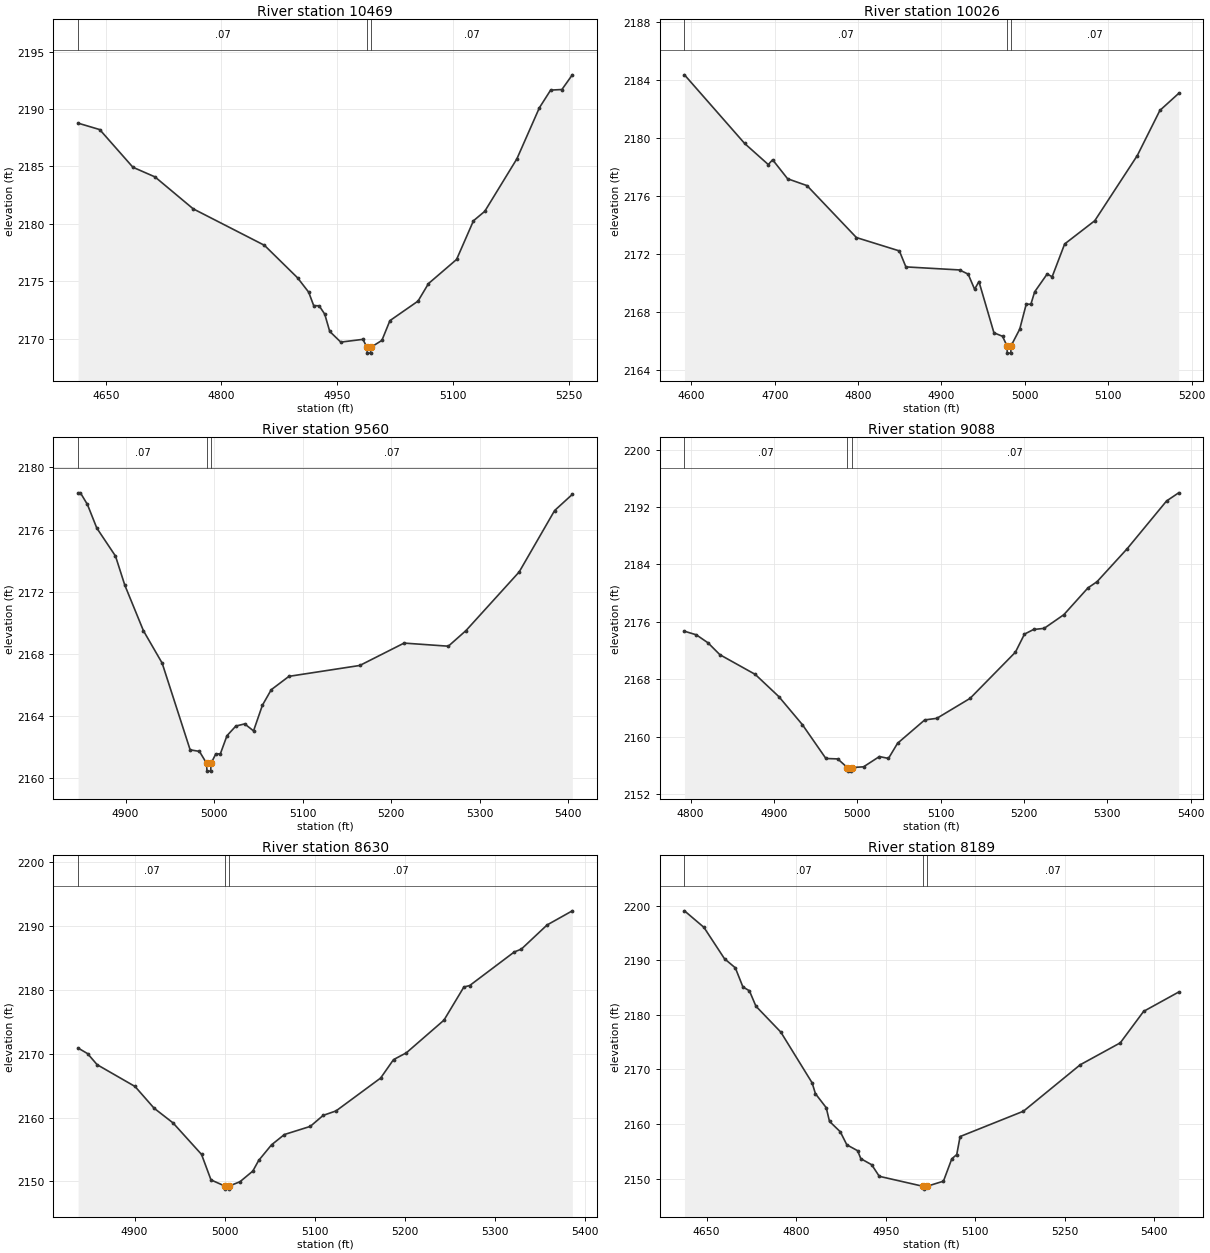
Type RM Length L Ch R = 1,10469,443,443,443
BEGIN DESCRIPTION:
Stream0241 23.0
END DESCRIPTION:
XS GIS Cut Line= 3
      1805125.01     13900325.02      1804875.00     13900025.00
      1804675.03     13899875.02
#Sta/Elev= 30
  4614.2 2188.77  4642.2 2188.21  4685.2 2184.93  4713.8 2184.09  4763.3 2181.31
  4855.7 2178.13  4898.6 2175.30  4913.0 2174.05  4919.5 2172.88  4926.6 2172.86
  4933.8 2172.14  4940.3 2170.63  4954.6 2169.70  4983.3 2169.94  4988.6 2169.24
  4989.0 2168.74  4993.2 2168.74  4993.5 2169.24  5007.9 2169.85  5018.3 2171.57
  5054.7 2173.27  5068.3 2174.80  5104.7 2176.90  5126.6 2180.27  5141.2 2181.09
  5182.9 2185.67  5212.0 2190.11  5226.6 2191.65  5241.2 2191.70  5254.7 2192.98
#Mann=3,-1,0
  4614.2    0.07       0  4988.6    0.05       0  4993.5    0.07       0
Bank Sta=4988.6,4993.5
Exp/Cntr=0.3,0.1

Type RM Length L Ch R = 1,10026,466,466,466
BEGIN DESCRIPTION:
Stream0241 22.0
END DESCRIPTION:
XS GIS Cut Line= 3
      1805275.01     13900125.04      1805175.00     13899725.00
      1805075.01     13899575.02
#Sta/Elev= 30
  4591.8 2184.36  4664.0 2179.63  4692.3 2178.18  4697.5 2178.51  4715.5 2177.20
  4738.7 2176.73  4798.0 2173.15  4849.5 2172.23  4857.3 2171.13  4921.7 2170.92
  4932.0 2170.63  4939.7 2169.59  4944.9 2170.12  4962.9 2166.59  4973.2 2166.35
  4978.5 2165.69  4978.9 2165.19  4983.1 2165.19  4983.4 2165.69  4993.8 2166.84
  5001.6 2168.56  5007.2 2168.56  5011.7 2169.41  5026.7 2170.64  5032.7 2170.45
  5047.7 2172.71  5083.8 2174.31  5134.8 2178.80  5161.9 2181.91  5184.4 2183.08
#Mann=3,-1,0
  4591.8    0.07       0  4978.5    0.05       0  4983.4    0.07       0
Bank Sta=4978.5,4983.4
Exp/Cntr=0.3,0.1

Type RM Length L Ch R = 1,9560,472,472,472
BEGIN DESCRIPTION:
Stream0241 21.0
END DESCRIPTION:
XS GIS Cut Line= 3
      1805675.00     13899824.99      1805625.00     13899675.00
      1805625.00     13899275.00
#Sta/Elev= 30
  4846.5 2178.37  4849.1 2178.37  4857.0 2177.62  4867.6 2176.10  4888.7 2174.30
  4899.2 2172.43  4920.3 2169.49  4941.4 2167.41  4973.0 2161.83  4983.5 2161.73
  4991.6 2160.96  4992.0 2160.46  4996.2 2160.46  4996.6 2160.96  5002.0 2161.57
  5007.1 2161.57  5014.6 2162.74  5024.6 2163.36  5034.6 2163.50  5044.6 2163.05
  5054.6 2164.70  5064.6 2165.70  5084.6 2166.56  5164.6 2167.26  5214.6 2168.70
  5264.6 2168.50  5284.6 2169.51  5344.6 2173.28  5384.6 2177.23  5404.6 2178.27
#Mann=3,-1,0
  4846.5    0.07       0  4991.6    0.05       0  4996.6    0.07       0
Bank Sta=4991.6,4996.6
Exp/Cntr=0.3,0.1

Type RM Length L Ch R = 1,9088,458,458,458
BEGIN DESCRIPTION:
Stream0241 20.0
END DESCRIPTION:
XS GIS Cut Line= 3
      1806125.03     13899525.03      1805975.00     13899375.00
      1805824.99     13899024.97
#Sta/Elev= 30
  4792.6 2174.70  4806.8 2174.20  4820.9 2173.08  4835.1 2171.43  4877.5 2168.69
  4905.8 2165.60  4934.1 2161.69  4962.3 2156.98  4976.5 2156.92  4988.0 2155.72
  4988.4 2155.22  4992.9 2155.22  4993.3 2155.72  5007.5 2155.82  5026.5 2157.25
  5037.4 2156.99  5048.3 2159.10  5080.9 2162.35  5095.4 2162.57  5135.3 2165.35
  5189.7 2171.78  5200.6 2174.30  5211.5 2174.94  5224.2 2175.10  5247.8 2177.00
  5276.8 2180.74  5287.6 2181.59  5323.9 2186.20  5371.1 2192.84  5385.6 2193.97
#Mann=3,-1,0
  4792.6    0.07       0  4988.0    0.05       0  4993.3    0.07       0
Bank Sta=4988,4993.3
Exp/Cntr=0.3,0.1

Type RM Length L Ch R = 1,8630,441,441,441
BEGIN DESCRIPTION:
Stream0241 19.0
END DESCRIPTION:
XS GIS Cut Line= 3
      1806374.99     13899274.97      1806325.00     13899125.00
      1806075.00     13898825.00
#Sta/Elev= 30
  4837.3 2170.86  4847.8 2169.99  4858.4 2168.26  4900.5 2164.85  4921.6 2161.46
  4942.7 2159.15  4974.3 2154.23  4984.8 2150.24  4999.9 2149.30  5000.3 2148.80
  5004.8 2148.80  5005.2 2149.30  5016.9 2149.95  5031.2 2151.62  5037.7 2153.28
  5052.0 2155.73  5066.3 2157.34  5095.0 2158.61  5109.3 2160.33  5123.6 2161.03
  5173.1 2166.17  5187.4 2169.05  5201.7 2170.12  5243.4 2175.22  5265.5 2180.40
  5272.0 2180.64  5321.5 2185.89  5329.3 2186.33  5357.9 2190.11  5385.9 2192.32
#Mann=3,-1,0
  4837.3    0.07       0  4999.9    0.05       0  5005.2    0.07       0
Bank Sta=4999.9,5005.2
Exp/Cntr=0.3,0.1

Type RM Length L Ch R = 1,8189,473,473,473
BEGIN DESCRIPTION:
Stream0241 18.0
END DESCRIPTION:
XS GIS Cut Line= 3
      1807024.98     13899024.99      1806675.00     13898875.00
      1806274.99     13898674.99
#Sta/Elev= 30
  4612.9 2199.08  4645.5 2196.05  4680.0 2190.29  4698.1 2188.63  4710.8 2185.13
  4721.7 2184.42  4732.6 2181.60  4774.3 2176.85  4826.8 2167.54  4832.3 2165.56
  4850.4 2162.99  4855.9 2160.48  4874.0 2158.57  4884.9 2156.19  4903.0 2155.10
  4908.4 2153.64  4926.6 2152.53  4939.3 2150.41  5013.3 2148.56  5013.8 2148.06
  5018.7 2148.56  5046.8 2149.52  5060.8 2153.62  5069.1 2154.40  5074.7 2157.70
  5180.9 2162.35  5276.0 2170.86  5343.1 2174.88  5382.2 2180.65  5440.9 2184.19
#Mann=3,-1,0
  4612.9    0.07       0  5013.3    0.05       0  5018.7    0.07       0
Bank Sta=5013.3,5018.7
Exp/Cntr=0.3,0.1

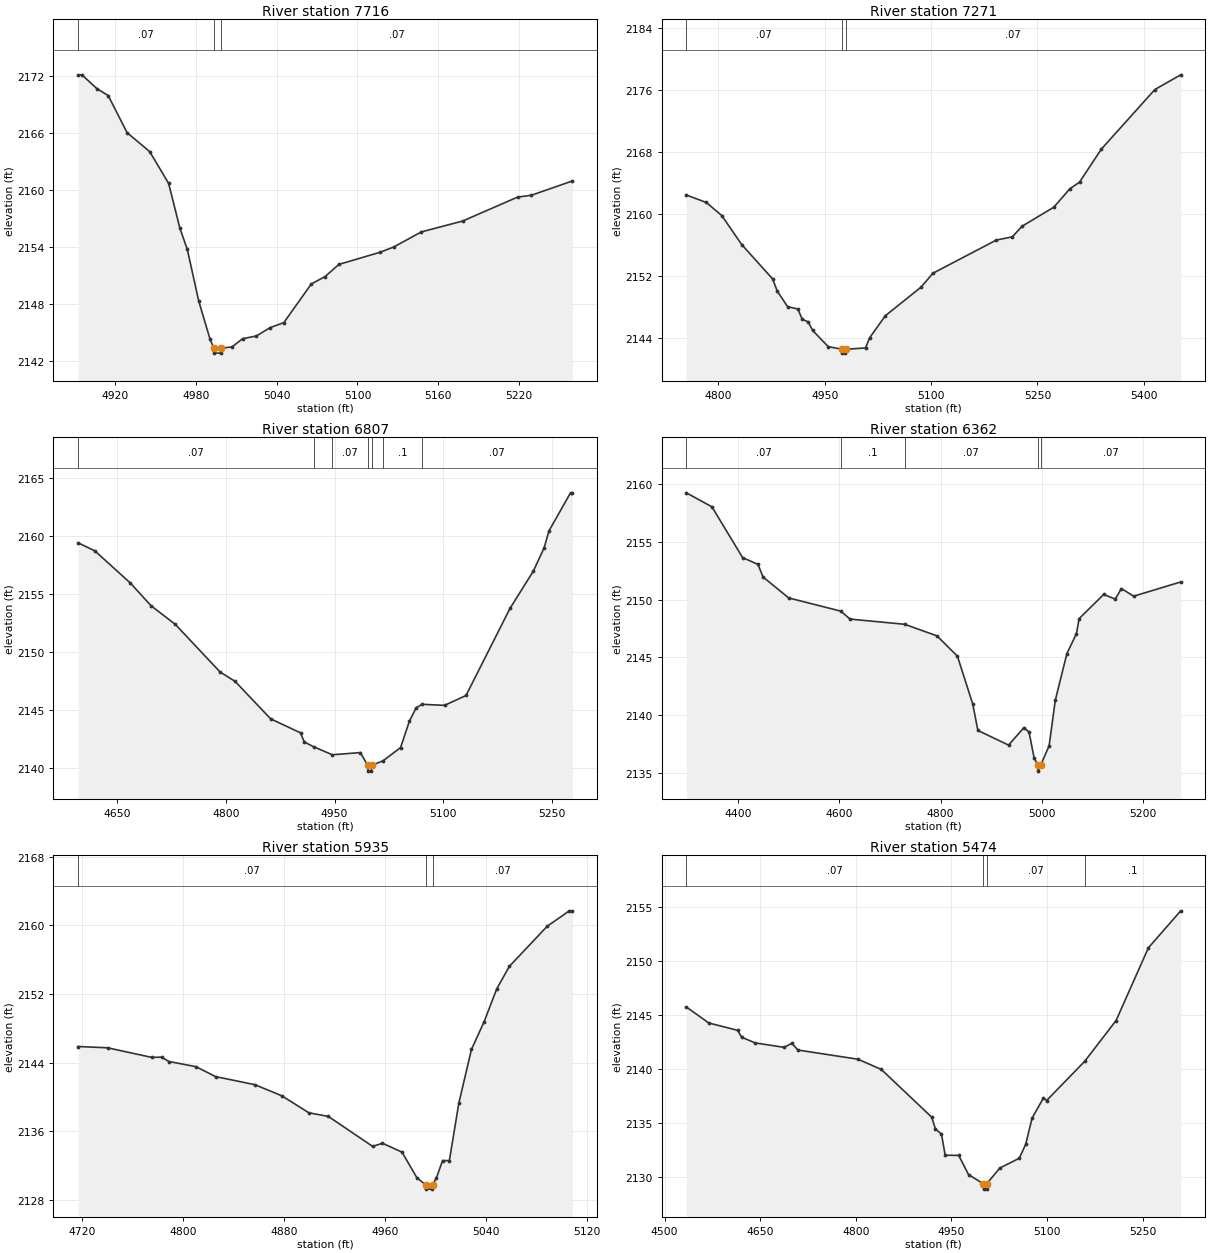
Type RM Length L Ch R = 1,7716,445,445,445
BEGIN DESCRIPTION:
Stream0241 17.0
END DESCRIPTION:
XS GIS Cut Line= 3
      1807124.99     13898674.99      1807025.00     13898625.00
      1806775.04     13898575.01
#Sta/Elev= 30
  4892.8 2172.13  4895.6 2172.13  4906.8 2170.67  4915.1 2169.95  4929.1 2166.05
  4945.9 2164.05  4959.9 2160.72  4968.3 2155.99  4973.8 2153.76  4982.2 2148.37
  4990.6 2144.35  4993.5 2143.36  4993.9 2142.86  4998.5 2142.86  4998.9 2143.36
  5007.1 2143.53  5014.8 2144.38  5025.0 2144.66  5035.2 2145.54  5045.4 2146.07
  5065.8 2150.14  5076.0 2150.91  5086.2 2152.19  5116.8 2153.47  5127.0 2154.03
  5147.4 2155.61  5178.0 2156.75  5218.8 2159.27  5228.9 2159.46  5259.5 2160.97
#Mann=3,-1,0
  4892.8    0.07       0  4993.5    0.05       0  4998.9    0.07       0
Bank Sta=4993.5,4998.9
Exp/Cntr=0.3,0.1

Type RM Length L Ch R = 1,7271,464,464,464
BEGIN DESCRIPTION:
Stream0241 16.0
END DESCRIPTION:
XS GIS Cut Line= 3
      1807324.97     13898424.97      1807175.00     13898225.00
      1806774.97     13898024.99
#Sta/Elev= 30
  4754.8 2162.45  4782.9 2161.49  4804.8 2159.79  4832.9 2156.04  4876.6 2151.59
  4882.9 2150.04  4897.5 2148.03  4912.0 2147.71  4918.3 2146.38  4926.6 2146.05
  4932.9 2144.94  4954.8 2142.86  4973.9 2142.51  4974.3 2142.01  4978.9 2142.01
  4979.4 2142.51  5007.6 2142.68  5013.1 2143.97  5035.5 2146.85  5085.8 2150.54
  5102.6 2152.34  5192.0 2156.63  5214.4 2157.04  5228.4 2158.42  5273.1 2160.88
  5295.4 2163.23  5309.4 2164.13  5340.2 2168.40  5415.6 2176.09  5452.0 2177.99
#Mann=3,-1,0
  4754.8    0.07       0  4973.9    0.05       0  4979.4    0.07       0
Bank Sta=4973.9,4979.4
Exp/Cntr=0.3,0.1

Type RM Length L Ch R = 1,6807,445,445,445
BEGIN DESCRIPTION:
Stream0241 15.0
END DESCRIPTION:
XS GIS Cut Line= 3
      1807475.00     13898224.98      1807375.00     13897825.00
      1807124.95     13897724.98
#Sta/Elev= 30
  4596.5 2159.45  4619.7 2158.75  4668.6 2155.98  4697.0 2154.03  4730.5 2152.42
  4792.3 2148.31  4812.9 2147.51  4861.9 2144.28  4903.1 2143.07  4908.3 2142.29
  4921.1 2141.87  4947.0 2141.18  4985.6 2141.37  4995.7 2140.27  4996.2 2139.77
  5000.8 2139.77  5001.2 2140.27  5016.9 2140.66  5041.1 2141.80  5053.2 2144.07
  5062.6 2145.23  5070.8 2145.53  5101.7 2145.44  5131.3 2146.29  5191.9 2153.79
  5224.2 2157.02  5239.0 2159.02  5245.7 2160.48  5275.4 2163.76  5278.1 2163.76
#Mann=7,-1,0
  4596.5    0.07       0  4921.1     0.1       0  4947.0    0.07       0
  4995.7    0.05       0  5001.2    0.07       0  5016.9     0.1       0
  5070.8    0.07       0
Bank Sta=4995.7,5001.2
Exp/Cntr=0.3,0.1

Type RM Length L Ch R = 1,6362,427,427,427
BEGIN DESCRIPTION:
Stream0241 14.0
END DESCRIPTION:
XS GIS Cut Line= 3
      1807575.00     13898225.02      1807675.00     13897525.00
      1807424.99     13897424.99
#Sta/Elev= 30
  4297.8 2159.23  4348.3 2158.02  4408.9 2153.63  4439.2 2153.04  4449.3 2151.95
  4499.9 2150.14  4602.7 2149.00  4621.1 2148.31  4729.0 2147.86  4792.8 2146.86
  4833.2 2145.10  4863.5 2140.96  4873.6 2138.68  4934.2 2137.41  4964.5 2138.92
  4974.6 2138.54  4984.7 2136.31  4992.1 2135.66  4992.5 2135.16  4997.6 2135.66
  5014.4 2137.37  5026.5 2141.29  5049.4 2145.32  5068.2 2147.04  5073.6 2148.35
  5122.1 2150.44  5144.9 2150.04  5157.1 2150.95  5181.3 2150.29  5274.2 2151.52
#Mann=5,-1,0
  4297.8    0.07       0  4602.7     0.1       0  4729.0    0.07       0
  4992.1    0.05       0  4997.6    0.07       0
Bank Sta=4992.1,4997.6
Exp/Cntr=0.3,0.1

Type RM Length L Ch R = 1,5935,461,461,461
BEGIN DESCRIPTION:
Stream0241 13.0
END DESCRIPTION:
XS GIS Cut Line= 3
      1807825.01     13897774.99      1808075.00     13897625.00
      1808075.00     13897525.03
#Sta/Elev= 30
  4717.0 2145.88  4740.3 2145.73  4775.3 2144.61  4783.1 2144.64  4788.9 2144.13
  4810.3 2143.53  4825.8 2142.37  4856.9 2141.43  4878.3 2140.13  4899.7 2138.15
  4915.2 2137.72  4950.2 2134.23  4958.0 2134.59  4973.5 2133.56  4985.2 2130.59
  4992.2 2129.74  4992.6 2129.24  4997.3 2129.24  4997.7 2129.74  5000.8 2130.56
  5005.6 2132.57  5011.0 2132.57  5018.5 2139.27  5028.5 2145.54  5038.5 2148.76
  5048.5 2152.60  5058.5 2155.23  5088.5 2159.91  5106.0 2161.71  5108.5 2161.71
#Mann=3,-1,0
  4717.0    0.07       0  4992.2    0.05       0  4997.7    0.07       0
Bank Sta=4992.2,4997.7
Exp/Cntr=0.3,0.1

Type RM Length L Ch R = 1,5474,470,470,470
BEGIN DESCRIPTION:
Stream0241 12.0
END DESCRIPTION:
XS GIS Cut Line= 3
      1808025.04     13898124.98      1808425.00     13897875.00
      1808375.00     13897574.99
#Sta/Elev= 30
  4534.1 2145.73  4569.4 2144.25  4614.8 2143.57  4620.7 2142.94  4642.0 2142.41
  4687.4 2142.00  4699.7 2142.37  4709.2 2141.75  4803.5 2140.90  4840.1 2139.95
  4919.1 2135.54  4925.0 2134.44  4934.4 2133.99  4940.3 2132.02  4961.5 2132.00
  4976.9 2130.23  5000.0 2129.38  5000.5 2128.88  5005.2 2128.88  5005.6 2129.38
  5026.0 2130.83  5056.4 2131.73  5066.6 2133.01  5076.7 2135.46  5094.5 2137.31
  5099.5 2137.08  5159.3 2140.71  5208.5 2144.48  5259.2 2151.21  5309.9 2154.63
#Mann=4,-1,0
  4534.1    0.07       0  5000.0    0.05       0  5005.6    0.07       0
  5159.3     0.1       0
Bank Sta=5000,5005.6
Exp/Cntr=0.3,0.1

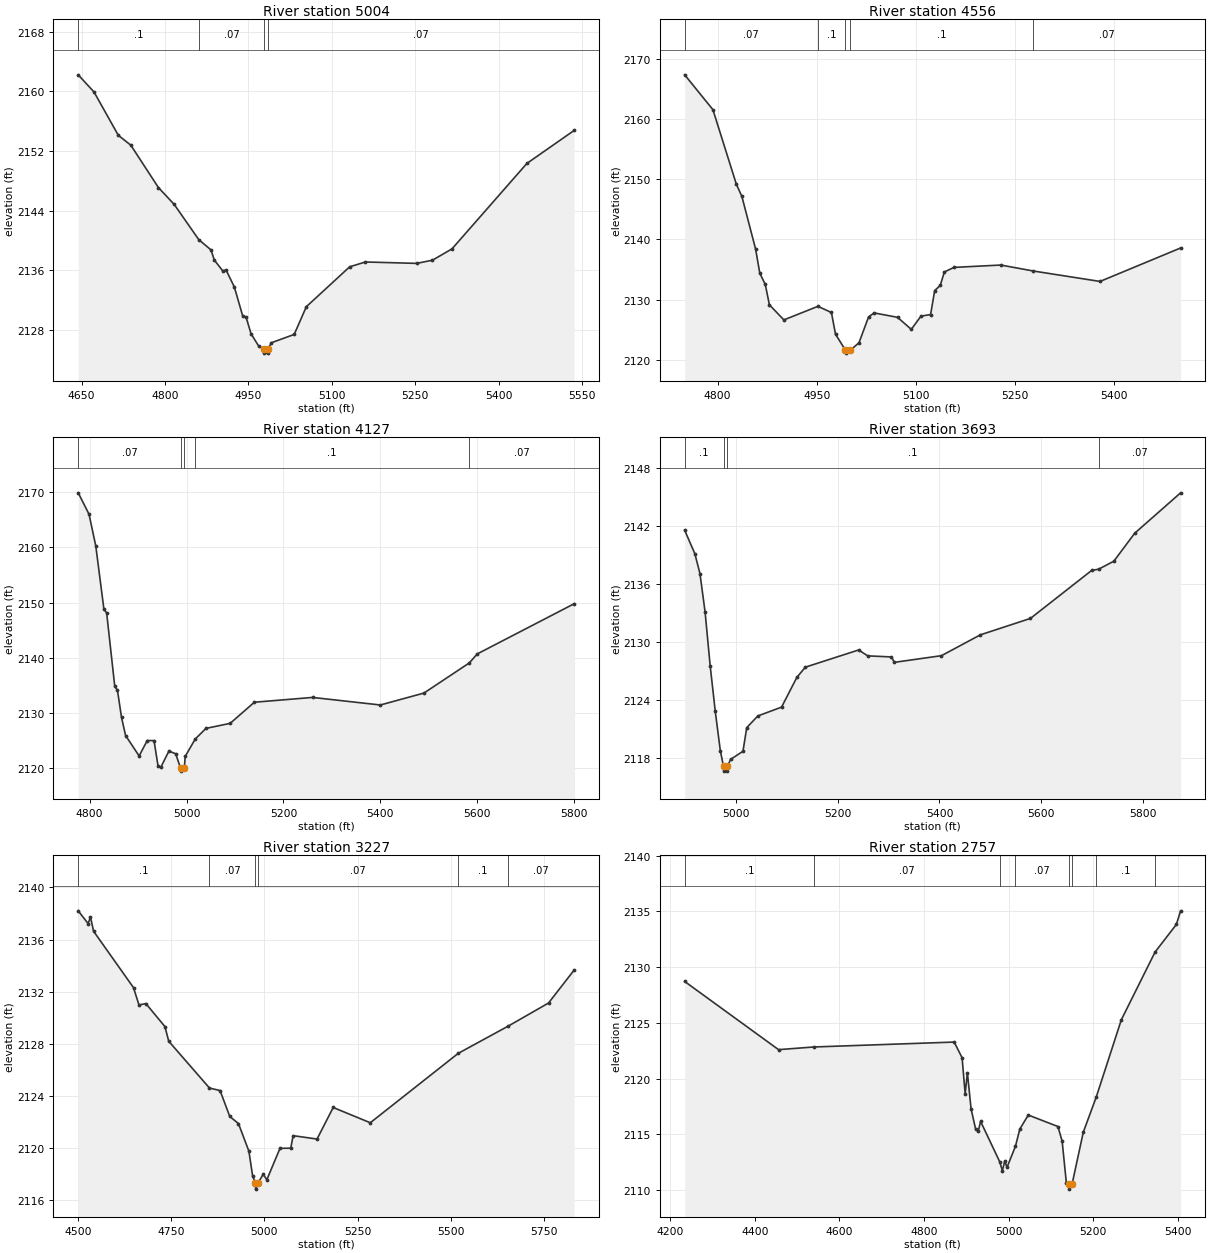
Type RM Length L Ch R = 1,5004,448,448,448
BEGIN DESCRIPTION:
Stream0241 11.0
END DESCRIPTION:
XS GIS Cut Line= 3
      1809024.97     13898174.96      1808825.00     13897875.00
      1808475.01     13897475.01
#Sta/Elev= 30
  4643.8 2162.23  4672.3 2159.92  4715.9 2154.12  4738.4 2152.79  4788.0 2147.11
  4816.5 2144.84  4860.6 2140.12  4882.6 2138.74  4888.6 2137.38  4903.7 2135.93
  4909.7 2136.05  4924.7 2133.75  4939.7 2129.86  4945.7 2129.71  4954.7 2127.48
  4968.3 2125.85  4978.0 2125.39  4978.5 2124.89  4985.1 2124.89  4985.6 2125.39
  4990.8 2126.27  5032.3 2127.40  5054.1 2131.12  5132.0 2136.47  5160.4 2137.12
  5252.5 2136.93  5281.0 2137.36  5316.1 2138.88  5450.9 2150.35  5535.8 2154.77
#Mann=4,-1,0
  4643.8     0.1       0  4860.6    0.07       0  4978.0    0.05       0
  4985.6    0.07       0
Bank Sta=4978,4985.6
Exp/Cntr=0.3,0.1

Type RM Length L Ch R = 1,4556,429,429,429
BEGIN DESCRIPTION:
Stream0241 10.0
END DESCRIPTION:
XS GIS Cut Line= 3
      1809425.01     13897875.01      1809225.00     13897725.00
      1808825.01     13897425.01
#Sta/Elev= 30
  4750.2 2167.30  4792.9 2161.52  4828.3 2149.17  4836.7 2147.13  4857.5 2138.38
  4863.8 2134.39  4872.1 2132.53  4878.3 2129.16  4900.2 2126.65  4951.7 2128.90
  4972.1 2127.88  4978.3 2124.28  4993.3 2121.64  4993.8 2121.14  5000.9 2121.64
  5013.8 2122.86  5028.3 2127.14  5036.7 2127.81  5072.1 2127.08  5092.9 2125.08
  5107.5 2127.27  5122.1 2127.54  5128.3 2131.52  5136.7 2132.37  5142.9 2134.60
  5157.5 2135.36  5228.3 2135.75  5277.5 2134.76  5378.3 2133.03  5500.2 2138.58
#Mann=5,-1,0
  4750.2    0.07       0  4951.7     0.1       0  4993.3    0.05       0
  5000.9     0.1       0  5277.5    0.07       0
Bank Sta=4993.3,5000.9
Exp/Cntr=0.3,0.1

Type RM Length L Ch R = 1,4127,434,434,434
BEGIN DESCRIPTION:
Stream0241 9.0
END DESCRIPTION:
XS GIS Cut Line= 3
      1809624.96     13897474.98      1809425.00     13897375.00
      1808624.96     13897375.00
#Sta/Elev= 30
  4776.4 2169.90  4798.7 2166.03  4812.7 2160.26  4829.5 2148.77  4835.1 2148.15
  4851.8 2134.87  4857.4 2134.13  4865.8 2129.21  4874.2 2125.94  4902.1 2122.24
  4918.9 2125.03  4932.9 2125.02  4941.3 2120.33  4946.9 2120.19  4963.6 2123.13
  4977.6 2122.63  4987.8 2119.99  4988.3 2119.49  4995.4 2119.99  4997.2 2122.15
  5017.8 2125.29  5040.0 2127.23  5090.0 2128.14  5140.0 2131.97  5260.0 2132.84
  5400.0 2131.47  5490.0 2133.63  5583.6 2139.09  5600.0 2140.72  5800.0 2149.81
#Mann=5,-1,0
  4776.4    0.07       0  4987.8    0.05       0  4995.4    0.07       0
  5017.8     0.1       0  5583.6    0.07       0
Bank Sta=4987.8,4995.4
Exp/Cntr=0.3,0.1

Type RM Length L Ch R = 1,3693,466,466,466
BEGIN DESCRIPTION:
Stream0241 8.0
END DESCRIPTION:
XS GIS Cut Line= 3
      1809625.00     13896975.00      1809525.00     13896975.00
      1808725.01     13897324.99
#Sta/Elev= 30
  4900.0 2141.59  4920.0 2139.16  4930.0 2137.10  4940.0 2133.15  4950.0 2127.57
  4960.0 2122.84  4970.0 2118.74  4976.2 2117.14  4976.7 2116.64  4983.4 2116.64
  4983.9 2117.14  4990.0 2117.85  5014.4 2118.70  5021.8 2121.15  5043.7 2122.36
  5090.1 2123.27  5120.1 2126.35  5136.8 2127.41  5241.3 2129.19  5259.2 2128.58
  5305.6 2128.47  5311.5 2127.91  5403.9 2128.60  5480.3 2130.76  5578.5 2132.46
  5698.6 2137.43  5712.4 2137.56  5742.2 2138.39  5783.2 2141.29  5873.2 2145.47
#Mann=4,-1,0
  4900.0     0.1       0  4976.2    0.05       0  4983.9     0.1       0
  5712.4    0.07       0
Bank Sta=4976.2,4983.9
Exp/Cntr=0.3,0.1

Type RM Length L Ch R = 1,3227,470,470,470
BEGIN DESCRIPTION:
Stream0241 7.0
END DESCRIPTION:
XS GIS Cut Line= 4
      1809895.79     13896731.22      1809797.87     13896594.57
      1809475.00     13896525.00      1808822.90     13897040.11
#Sta/Elev= 30
  4501.1 2138.20  4527.7 2137.22  4533.9 2137.73  4542.4 2136.63  4649.3 2132.31
  4664.0 2130.98  4682.4 2131.09  4733.4 2129.33  4743.8 2128.20  4853.0 2124.61
  4881.3 2124.42  4907.4 2122.43  4930.6 2121.89  4958.6 2119.77  4968.8 2117.84
  4976.1 2117.36  4976.6 2116.86  4983.8 2117.36  4996.9 2118.00  5006.7 2117.58
  5042.0 2119.99  5070.8 2120.00  5077.2 2120.96  5141.3 2120.70  5184.6 2123.12
  5284.0 2121.95  5519.7 2127.27  5653.1 2129.35  5761.8 2131.13  5830.5 2133.66
#Mann=6,-1,0
  4501.1     0.1       0  4853.0    0.07       0  4976.1    0.05       0
  4983.8    0.07       0  5519.7     0.1       0  5653.1    0.07       0
Bank Sta=4976.1,4983.8
Exp/Cntr=0.3,0.1

Type RM Length L Ch R = 1,2757,427,427,427
BEGIN DESCRIPTION:
Stream0241 6.0
END DESCRIPTION:
XS GIS Cut Line= 4
      1809873.32     13896556.89      1809646.31     13896253.17
      1809275.00     13896125.00      1808874.99     13896125.00
#Sta/Elev= 30
  4234.4 2128.72  4456.2 2122.60  4540.0 2122.84  4871.3 2123.28  4890.0 2121.87
  4897.2 2118.63  4902.5 2120.53  4911.2 2117.29  4921.8 2115.49  4928.4 2115.29
  4933.7 2116.16  4979.1 2112.52  4985.2 2111.72  4990.8 2112.62  4996.1 2112.03
  5016.1 2113.93  5026.4 2115.47  5046.4 2116.73  5116.4 2115.70  5126.4 2114.40
  5136.4 2110.63  5142.5 2110.58  5143.0 2110.08  5150.2 2110.58  5176.4 2115.19
  5207.0 2118.34  5266.4 2125.29  5346.0 2131.36  5396.4 2133.84  5406.4 2135.06
#Mann=8,-1,0
  4234.4     0.1       0  4540.0    0.07       0  4979.1     0.1       0
  5016.1    0.07       0  5142.5    0.05       0  5150.2    0.07       0
  5207.0     0.1       0  5346.0    0.07       0
Bank Sta=5142.5,5150.2
Exp/Cntr=0.3,0.1

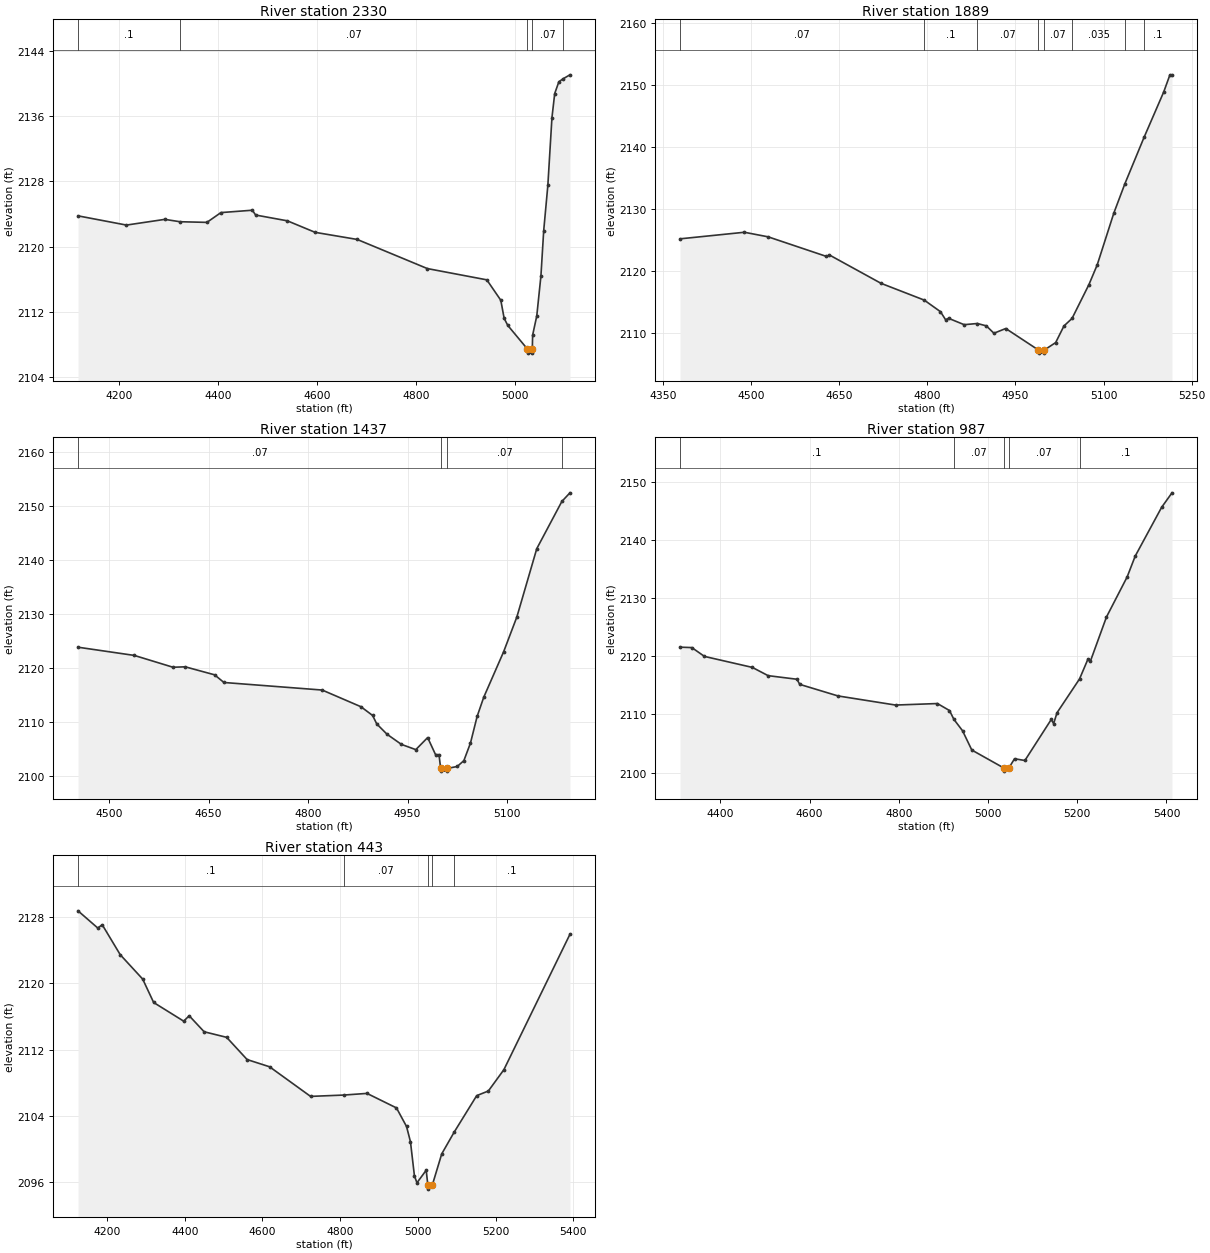
Type RM Length L Ch R = 1,2330,441,441,441
BEGIN DESCRIPTION:
Stream0241 5.0
END DESCRIPTION:
XS GIS Cut Line= 3
      1809868.73     13896429.37      1809275.00     13895775.00
      1809224.99     13895674.98
#Sta/Elev= 30
  4116.2 2123.76  4214.2 2122.63  4291.9 2123.33  4322.4 2123.04  4377.0 2122.96
  4405.4 2124.16  4468.9 2124.45  4475.7 2123.86  4539.9 2123.15  4596.0 2121.74
  4681.1 2120.87  4823.1 2117.30  4943.4 2115.92  4971.7 2113.42  4978.5 2111.20
  4985.9 2110.33  5025.6 2107.44  5026.1 2106.94  5035.0 2106.94  5035.5 2107.44
  5036.1 2109.14  5044.5 2111.50  5052.9 2116.40  5058.5 2121.93  5066.9 2127.49
  5075.2 2135.79  5080.8 2138.75  5089.2 2140.19  5097.6 2140.55  5111.6 2141.04
#Mann=5,-1,0
  4116.2     0.1       0  4322.4    0.07       0  5025.6    0.05       0
  5035.5    0.07       0  5097.6     0.1       0
Bank Sta=5025.6,5035.5
Exp/Cntr=0.3,0.1

Type RM Length L Ch R = 1,1889,452,452,452
BEGIN DESCRIPTION:
Stream0241 4.0
END DESCRIPTION:
XS GIS Cut Line= 3
      1809717.25     13896143.32      1809625.00     13895525.00
      1809775.01     13895374.99
#Sta/Elev= 30
  4379.1 2125.14  4488.6 2126.20  4529.1 2125.46  4628.3 2122.30  4633.4 2122.53
  4721.2 2117.96  4794.6 2115.26  4822.3 2113.39  4831.1 2112.08  4836.1 2112.32
  4862.7 2111.29  4885.1 2111.48  4900.4 2111.10  4913.3 2109.91  4933.5 2110.67
  4989.1 2107.20  4989.6 2106.70  4998.6 2106.70  4999.1 2107.20  5018.4 2108.40
  5032.5 2111.08  5046.3 2112.30  5075.0 2117.75  5089.1 2120.93  5117.4 2129.29
  5136.2 2134.02  5168.9 2141.52  5202.3 2148.83  5212.9 2151.60  5216.4 2151.60
#Mann=8,-1,0
  4379.1    0.07       0  4794.6     0.1       0  4885.1    0.07       0
  4989.1    0.05       0  4999.1    0.07       0  5046.3   0.035       0
  5136.2    0.07       0  5168.9     0.1       0
Bank Sta=4989.1,4999.1
Exp/Cntr=0.3,0.1

Type RM Length L Ch R = 1,1437,450,450,450
BEGIN DESCRIPTION:
Stream0241 3.0
END DESCRIPTION:
XS GIS Cut Line= 3
      1809815.91     13896175.04      1810025.00     13895675.00
      1810025.00     13895475.00
#Sta/Elev= 30
  4453.0 2123.85  4537.9 2122.33  4596.3 2120.14  4614.7 2120.22  4659.0 2118.74
  4673.1 2117.32  4821.3 2115.92  4879.8 2112.83  4897.4 2111.21  4903.6 2109.65
  4919.1 2107.74  4940.8 2105.86  4962.5 2104.89  4980.4 2107.12  4992.3 2103.96
  4997.5 2103.96  5000.0 2101.41  5000.5 2100.91  5009.5 2100.91  5010.0 2101.41
  5025.0 2101.77  5035.0 2102.85  5045.0 2106.12  5055.0 2111.03  5065.0 2114.59
  5095.0 2123.01  5115.0 2129.47  5145.0 2142.10  5182.8 2150.83  5195.0 2152.43
#Mann=4,-1,0
  4453.0    0.07       0  5000.0    0.05       0  5010.0    0.07       0
  5182.8     0.1       0
Bank Sta=5000,5010
Exp/Cntr=0.3,0.1

Type RM Length L Ch R = 1,987,544,544,544
BEGIN DESCRIPTION:
Stream0241 2.0
END DESCRIPTION:
XS GIS Cut Line= 3
      1810012.50     13896378.89      1810425.00     13895825.00
      1810325.01     13895425.02
#Sta/Elev= 30
  4309.4 2121.57  4335.8 2121.50  4364.1 2119.98  4471.4 2118.09  4506.8 2116.67
  4571.5 2116.05  4577.7 2115.17  4663.4 2113.18  4792.5 2111.61  4886.4 2111.87
  4913.4 2110.67  4923.5 2109.13  4942.7 2107.19  4963.5 2103.87  5036.2 2100.74
  5036.7 2100.24  5046.2 2100.74  5059.3 2102.37  5082.5 2102.07  5141.7 2109.14
  5146.9 2108.41  5154.6 2110.29  5205.0 2116.10  5224.2 2119.57  5229.4 2119.16
  5265.4 2126.76  5311.8 2133.66  5329.9 2137.25  5389.1 2145.64  5412.3 2148.13
#Mann=5,-1,0
  4309.4     0.1       0  4923.5    0.07       0  5036.2    0.05       0
  5046.2    0.07       0  5205.0     0.1       0
Bank Sta=5036.2,5046.2
Exp/Cntr=0.3,0.1

Type RM Length L Ch R = 1,443,0,0,0
BEGIN DESCRIPTION:
Stream0241 1.0
END DESCRIPTION:
XS GIS Cut Line= 3
      1811039.97     13896826.37      1810878.10     13895956.95
      1810875.00     13895575.02
#Sta/Elev= 30
  4125.1 2128.75  4175.9 2126.68  4187.5 2127.07  4233.8 2123.46  4291.6 2120.52
  4319.8 2117.70  4397.1 2115.45  4411.3 2116.10  4449.8 2114.17  4507.7 2113.50
  4560.4 2110.82  4618.2 2109.95  4723.7 2106.38  4809.0 2106.54  4869.0 2106.74
  4944.9 2104.99  4970.8 2102.75  4980.9 2100.91  4991.1 2096.80  4997.6 2095.96
  5021.4 2097.48  5025.6 2095.70  5026.1 2095.20  5037.2 2095.70  5061.4 2099.45
  5093.0 2102.04  5151.4 2106.47  5181.4 2107.03  5221.4 2109.60  5391.4 2125.92
#Mann=5,-1,0
  4125.1     0.1       0  4809.0    0.07       0  5025.6    0.05       0
  5037.2    0.07       0  5093.0     0.1       0
Bank Sta=5025.6,5037.2
Exp/Cntr=0.3,0.1

Chan Stop Cuts=-1