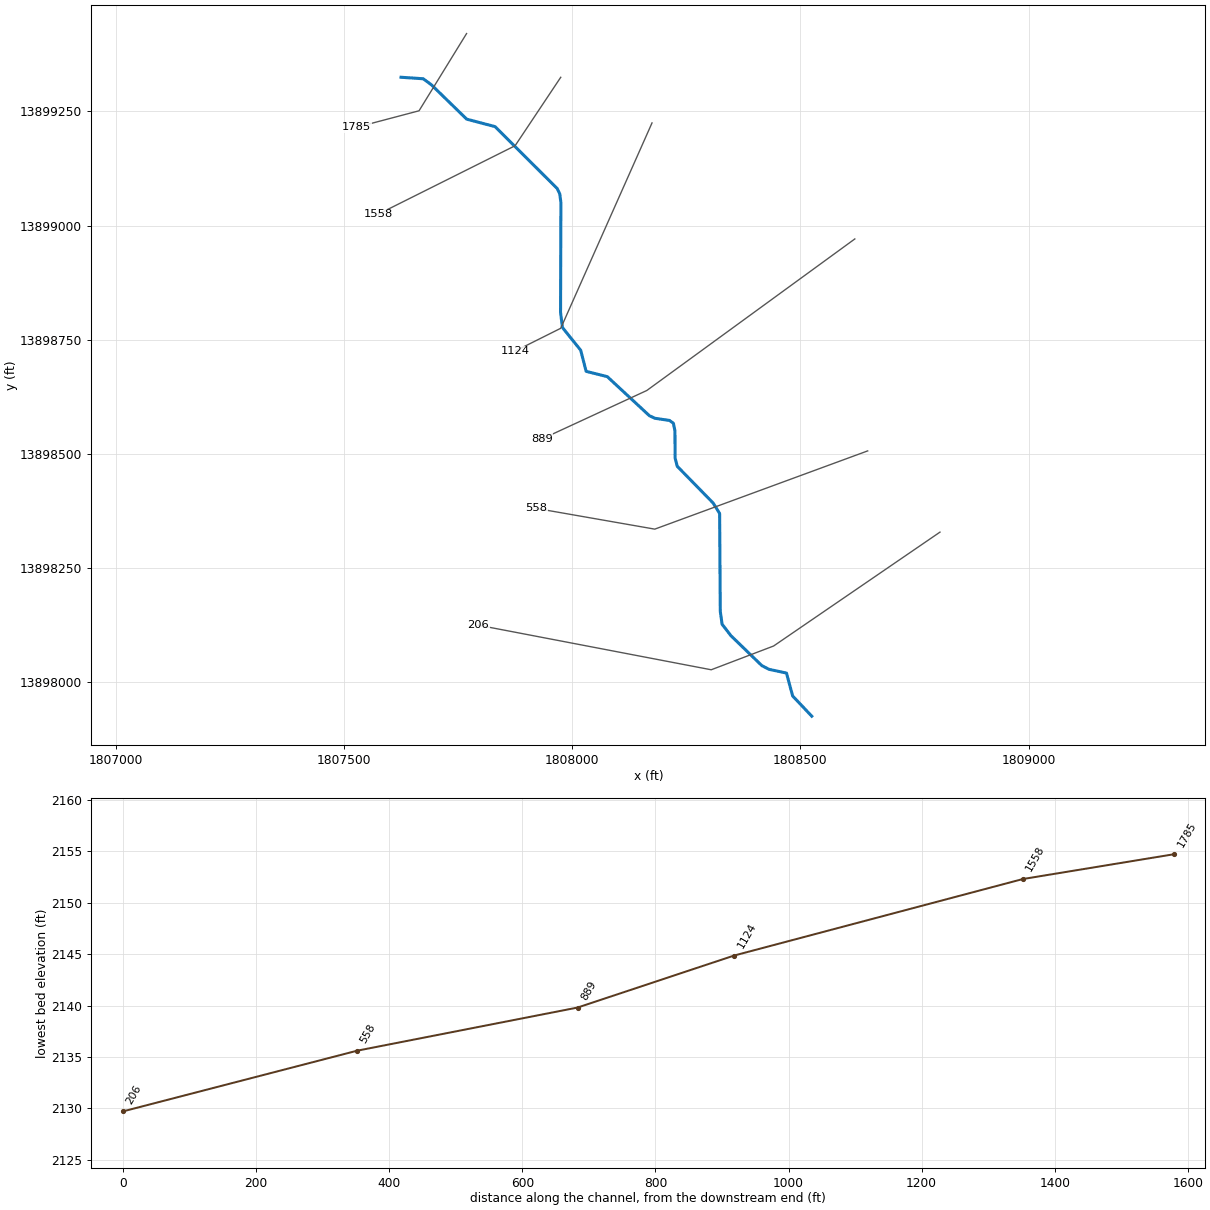
--- Stream0243.prj (project) ---

Proj Title=Stream0243 Base Level Engineering
Current Plan=p01
Default Exp/Contr=0.3,0.1
English Units
Geom File=g01
Flow File=f01
Plan File=p01
Y Axis Title=Elevation
X Axis Title(PF)=Main Channel Distance
X Axis Title(XS)=Station
BEGIN DESCRIPTION:
Stream0243
END DESCRIPTION:
DSS Export Rating Curves= 0
DSS Export Rating Curve Sorted= 0
DSS Export Volume Flow Curves= 0
DXF OffsetX= 0
DXF OffsetY= 0
DXF ScaleX= 1
DXF ScaleY= 10

--- Stream0243.p01 (plan) ---

Plan Title=Multiple Run
Short Identifier=Multiple
Geom File=g01
Flow File=f01
Subcritical Flow
K Sum by GR= 0
Std Step Tol= 0.01
Critical Tol= 0.01
Num of Std Step Trials= 20
Max Error Tol= 0.3
Flow Tol Ratio= 0.001
Split Flow NTrial= 30
Split Flow Tol= 0.02
Split Flow Ratio= 0.02
Log Output Level= 0
Friction Slope Method= 1
Unsteady Friction Slope Method= 2
Unsteady Bridges Friction Slope Method= 1
Parabolic Critical Depth
Global Vel Dist=  1 , 1 , 1
Global Log Level= 0
CheckData=True
Encroach Param= -1, 0, 0, 0
BEGIN DESCRIPTION:
Multiple Run
END DESCRIPTION:

--- Stream0243.f01 (steady flow) ---

Flow Title=Multiple
Program Version=4.10
Number of Profiles= 7
Profile Names=10-year,25-year,50-year,1pct_min,100-year,1pct_plu,500-year
River Rch & RM=Stream0243,Reach-1         ,1785
     958    1634    2275    1532    3056    6098    5453
Boundary for River Rch & Prof#=Stream0243,Reach-1         , 1
Up Type= 0
Dn Type= 3
Dn Slope=0.01
Boundary for River Rch & Prof#=Stream0243,Reach-1         , 2
Up Type= 0
Dn Type= 3
Dn Slope=0.01
Boundary for River Rch & Prof#=Stream0243,Reach-1         , 3
Up Type= 0
Dn Type= 3
Dn Slope=0.01
Boundary for River Rch & Prof#=Stream0243,Reach-1         , 4
Up Type= 0
Dn Type= 3
Dn Slope=0.01
Boundary for River Rch & Prof#=Stream0243,Reach-1         , 5
Up Type= 0
Dn Type= 3
Dn Slope=0.01
Boundary for River Rch & Prof#=Stream0243,Reach-1         , 6
Up Type= 0
Dn Type= 3
Dn Slope=0.01
Boundary for River Rch & Prof#=Stream0243,Reach-1         , 7
Up Type= 0
Dn Type= 3
Dn Slope=0.01
DSS Import GetInterval= 0
DSS Import GetPeak= 0
DSS Import FillOption= 0

--- Stream0243.g01 (geometry) ---

Geom Title=Existing Conditions

River Reach=Stream0243,Reach-1
Reach XY= 30
      1807625.00     13899325.00      1807673.64     13899321.71
      1807691.69     13899308.38      1807768.95     13899233.16
      1807831.05     13899216.84      1807967.19     13899081.19
      1807972.94     13899069.15      1807975.30     13899050.12
      1807974.56     13898809.81      1807978.74     13898776.52
      1808018.72     13898726.84      1808030.59     13898680.61
      1808076.95     13898668.99      1808169.30     13898583.32
      1808181.52     13898577.73      1808213.28     13898573.01
      1808221.88     13898566.69      1808225.21     13898550.18
      1808225.61     13898490.38      1808230.26     13898472.53
      1808308.92     13898392.06      1808323.11     13898369.22
      1808324.57     13898154.82      1808328.53     13898126.45
      1808347.84     13898101.42      1808415.55     13898035.86
      1808431.41     13898027.66      1808469.56     13898019.49
      1808483.12     13897969.30      1808525.00     13897925.00

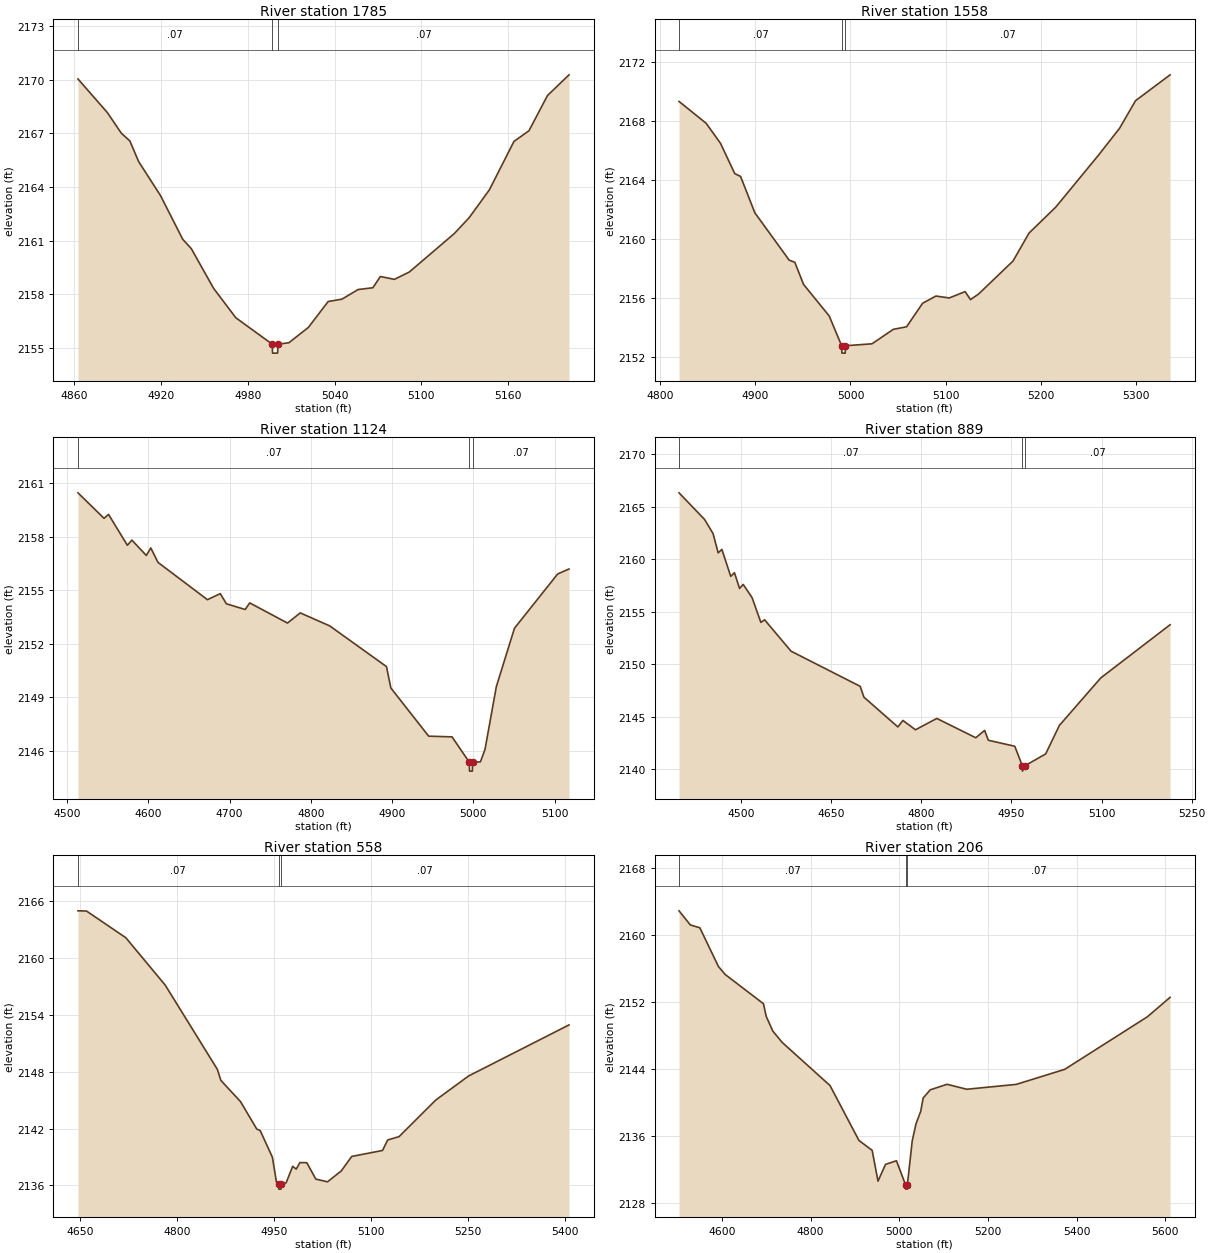
Type RM Length L Ch R = 1,1785,227,227,227
BEGIN DESCRIPTION:
Stream0243 3.0
END DESCRIPTION:
XS GIS Cut Line= 3
      1807768.64     13899420.78      1807664.48     13899251.53
      1807528.19     13899215.52
#Sta/Elev= 30
  4862.5 2170.05  4882.9 2168.16  4892.5 2167.01  4898.4 2166.58  4904.5 2165.42
  4919.6 2163.52  4935.0 2161.07  4940.9 2160.55  4956.3 2158.33  4971.7 2156.68
  4996.9 2155.20  4997.1 2154.70  5000.6 2154.70  5000.9 2155.20  5008.4 2155.28
  5021.9 2156.14  5035.6 2157.59  5045.1 2157.72  5056.3 2158.26  5066.5 2158.36
  5071.7 2158.99  5081.4 2158.83  5091.7 2159.24  5122.8 2161.39  5133.1 2162.28
  5147.1 2163.84  5164.1 2166.55  5174.5 2167.15  5187.3 2169.12  5202.2 2170.28
#Mann=3,-1,0
  4862.5    0.07       0  4996.9    0.05       0  5000.9    0.07       0
Bank Sta=4996.9,5000.9
Exp/Cntr=0.3,0.1

Type RM Length L Ch R = 1,1558,434,434,434
BEGIN DESCRIPTION:
Stream0243 2.0
END DESCRIPTION:
XS GIS Cut Line= 3
      1807974.98     13899324.97      1807875.00     13899175.00
      1807575.04     13899025.02
#Sta/Elev= 30
  4820.0 2169.31  4848.5 2167.83  4863.5 2166.48  4878.5 2164.43  4884.6 2164.24
  4899.6 2161.78  4935.6 2158.58  4941.6 2158.43  4950.7 2156.94  4977.7 2154.80
  4990.7 2152.79  4991.0 2152.29  4994.5 2152.29  4994.7 2152.79  5022.6 2152.92
  5045.0 2153.90  5058.9 2154.07  5075.7 2155.66  5089.7 2156.15  5103.7 2156.02
  5120.4 2156.45  5126.0 2155.91  5134.4 2156.28  5170.7 2158.52  5187.5 2160.41
  5215.5 2162.16  5260.2 2165.66  5282.5 2167.49  5299.3 2169.36  5335.6 2171.11
#Mann=3,-1,0
  4820.0    0.07       0  4990.7    0.05       0  4994.7    0.07       0
Bank Sta=4990.7,4994.7
Exp/Cntr=0.3,0.1

Type RM Length L Ch R = 1,1124,235,235,235
BEGIN DESCRIPTION:
Stream0243 1.0
END DESCRIPTION:
XS GIS Cut Line= 3
      1808174.99     13899224.97      1807975.00     13898775.00
      1807875.01     13898725.01
#Sta/Elev= 30
  4513.5 2160.45  4545.6 2159.02  4551.1 2159.24  4574.3 2157.51  4579.8 2157.80
  4597.6 2156.94  4603.1 2157.36  4612.0 2156.55  4672.8 2154.46  4688.6 2154.80
  4696.1 2154.23  4719.3 2153.91  4724.8 2154.28  4771.3 2153.15  4787.0 2153.72
  4823.3 2152.99  4893.1 2150.71  4898.5 2149.51  4945.0 2146.81  4973.8 2146.77
  4995.0 2145.35  4995.3 2144.85  4998.8 2144.85  4999.0 2145.35  5008.7 2145.37
  5014.3 2146.06  5028.3 2149.59  5050.6 2152.86  5103.7 2155.90  5117.7 2156.18
#Mann=3,-1,0
  4513.5    0.07       0  4995.0    0.05       0  4999.0    0.07       0
Bank Sta=4995,4999
Exp/Cntr=0.3,0.1

Type RM Length L Ch R = 1,889,331,331,331
BEGIN DESCRIPTION:
Stream0243 0.2
END DESCRIPTION:
XS GIS Cut Line= 3
      1808619.36     13898970.72      1808163.62     13898638.68
      1807933.58     13898532.34
#Sta/Elev= 30
  4396.7 2166.32  4439.2 2163.78  4453.3 2162.44  4461.8 2160.60  4468.0 2160.93
  4482.7 2158.36  4488.9 2158.71  4497.4 2157.21  4503.5 2157.59  4518.2 2156.34
  4532.9 2153.97  4539.1 2154.22  4583.1 2151.23  4698.2 2147.88  4704.4 2146.85
  4760.9 2144.01  4769.3 2144.63  4790.2 2143.74  4825.7 2144.82  4890.6 2142.98
  4905.3 2143.68  4911.5 2142.74  4955.5 2142.17  4968.1 2140.30  4968.3 2139.80
  4972.1 2140.30  5006.9 2141.44  5029.8 2144.16  5098.6 2148.68  5214.0 2153.75
#Mann=3,-1,0
  4396.7    0.07       0  4968.1    0.05       0  4972.1    0.07       0
Bank Sta=4968.1,4972.1
Exp/Cntr=0.3,0.1

Type RM Length L Ch R = 1,558,352,352,352
BEGIN DESCRIPTION:
Stream0243 0.1
END DESCRIPTION:
XS GIS Cut Line= 3
      1808647.55     13898506.30      1808180.98     13898334.86
      1807921.79     13898380.22
#Sta/Elev= 30
  4646.2 2164.98  4659.4 2164.96  4720.3 2162.14  4781.3 2157.14  4862.0 2148.25
  4867.4 2147.09  4897.8 2144.85  4923.0 2141.95  4928.3 2141.79  4947.2 2138.98
  4953.5 2136.35  4956.8 2136.11  4957.1 2135.61  4960.6 2135.61  4960.8 2136.11
  4968.5 2136.28  4978.6 2138.02  4984.0 2137.72  4989.8 2138.41  5000.5 2138.40
  5014.4 2136.67  5032.5 2136.38  5053.8 2137.53  5070.1 2139.06  5117.7 2139.69
  5125.7 2140.80  5143.3 2141.15  5200.1 2145.01  5250.9 2147.55  5406.4 2152.94
#Mann=3,-1,0
  4646.2    0.07       0  4956.8    0.05       0  4960.8    0.07       0
Bank Sta=4956.8,4960.8
Exp/Cntr=0.3,0.1

Type RM Length L Ch R = 1,206,0,0,0
BEGIN DESCRIPTION:
Stream0243 0.0
END DESCRIPTION:
XS GIS Cut Line= 4
      1808805.98     13898328.35      1808441.39     13898078.78
      1808304.68     13898026.70      1807794.66     13898124.36
#Sta/Elev= 30
  4503.4 2162.87  4528.8 2161.19  4550.3 2160.85  4592.2 2156.24  4607.1 2155.30
  4693.8 2151.80  4699.9 2150.30  4714.8 2148.55  4735.8 2147.20  4843.9 2142.05
  4909.1 2135.51  4938.9 2134.33  4952.1 2130.66  4969.0 2132.66  4993.7 2133.09
  5014.3 2130.21  5014.5 2129.71  5018.0 2129.71  5018.3 2130.21  5029.2 2135.43
  5037.7 2137.48  5048.4 2138.98  5053.9 2140.56  5069.8 2141.54  5107.8 2142.20
  5152.3 2141.61  5263.9 2142.19  5373.1 2143.98  5559.5 2150.24  5610.8 2152.56
#Mann=3,-1,0
  4503.4    0.07       0  5014.3    0.05       0  5018.3    0.07       0
Bank Sta=5014.3,5018.3
Exp/Cntr=0.3,0.1

Chan Stop Cuts=-1