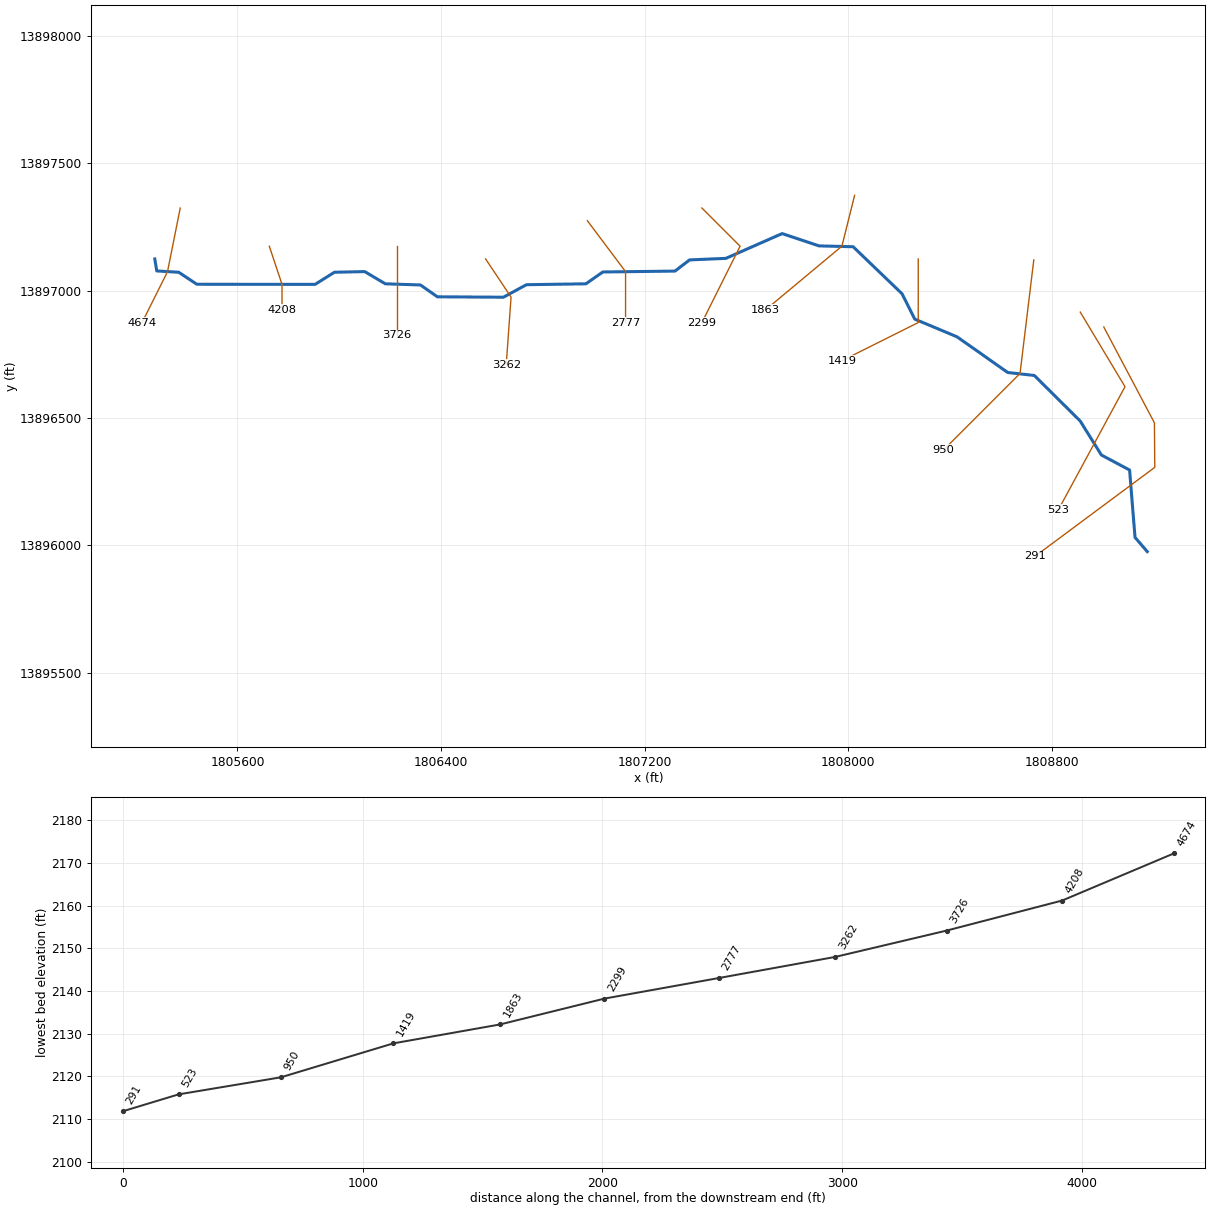
--- Stream0244.prj (project) ---

Proj Title=Stream0244 Base Level Engineering
Current Plan=p01
Default Exp/Contr=0.3,0.1
English Units
Geom File=g01
Flow File=f01
Plan File=p01
BEGIN DESCRIPTION:
Stream0244
END DESCRIPTION:

--- Stream0244.p01 (plan) ---

Plan Title=Multiple Run
Short Identifier=Multiple
Geom File=g01
Flow File=f01
Subcritical Flow
K Sum by GR= 0
Std Step Tol= 0.01
Critical Tol= 0.01
Num of Std Step Trials= 20
Max Error Tol= 0.3
Flow Tol Ratio= 0.001
Split Flow NTrial= 30
Split Flow Tol= 0.02
Split Flow Ratio= 0.02
Log Output Level= 0
Friction Slope Method= 1
Unsteady Friction Slope Method= 2
Unsteady Bridges Friction Slope Method= 1
Parabolic Critical Depth
Global Vel Dist=  1 , 1 , 1
Global Log Level= 0
CheckData=True
Encroach Param= -1, 0, 0, 0
BEGIN DESCRIPTION:
Multiple Run
END DESCRIPTION:

--- Stream0244.f01 (steady flow) ---

Flow Title=Multiple
Number of Profiles=7
Profile Names=10-year,25-year,50-year,1pct_min,100-year,1pct_plu,500-year
River Rch & RM= Stream0244,Reach-1,4674
    1023    1741    2422    1628    3248    6481    5778
Boundary for River Rch & Prof#=Stream0244,Reach-1,1
Up Type=0
Dn Type=3
Dn Slope=0.005
Boundary for River Rch & Prof#=Stream0244,Reach-1,2
Up Type=0
Dn Type=3
Dn Slope=0.005
Boundary for River Rch & Prof#=Stream0244,Reach-1,3
Up Type=0
Dn Type=3
Dn Slope=0.005
Boundary for River Rch & Prof#=Stream0244,Reach-1,4
Up Type=0
Dn Type=3
Dn Slope=0.005
Boundary for River Rch & Prof#=Stream0244,Reach-1,5
Up Type=0
Dn Type=3
Dn Slope=0.005
Boundary for River Rch & Prof#=Stream0244,Reach-1,6
Up Type=0
Dn Type=3
Dn Slope=0.005
Boundary for River Rch & Prof#=Stream0244,Reach-1,7
Up Type=0
Dn Type=3
Dn Slope=0.005

--- Stream0244.g01 (geometry) ---

Geom Title=Existing Conditions

River Reach=Stream0244,Reach-1
Reach XY= 30
      1805275.00     13897125.00      1805282.76     13897077.84
      1805368.99     13897072.69      1805440.21     13897025.52
      1805904.97     13897025.07      1805980.94     13897072.75
      1806100.07     13897075.23      1806180.94     13897027.27
      1806319.06     13897022.73      1806385.50     13896976.22
      1806645.15     13896974.64      1806735.50     13897023.78
      1806969.06     13897027.26      1807035.50     13897073.78
      1807319.06     13897077.26      1807376.57     13897121.21
      1807519.06     13897127.27      1807740.27     13897224.62
      1807885.51     13897176.23      1808019.14     13897172.93
      1808211.36     13896988.20      1808261.43     13896888.47
      1808427.29     13896819.15      1808626.59     13896678.83
      1808731.17     13896667.14      1808911.37     13896488.21
      1808994.77     13896354.59      1809105.56     13896295.55
      1809126.89     13896030.78      1809175.00     13895975.00

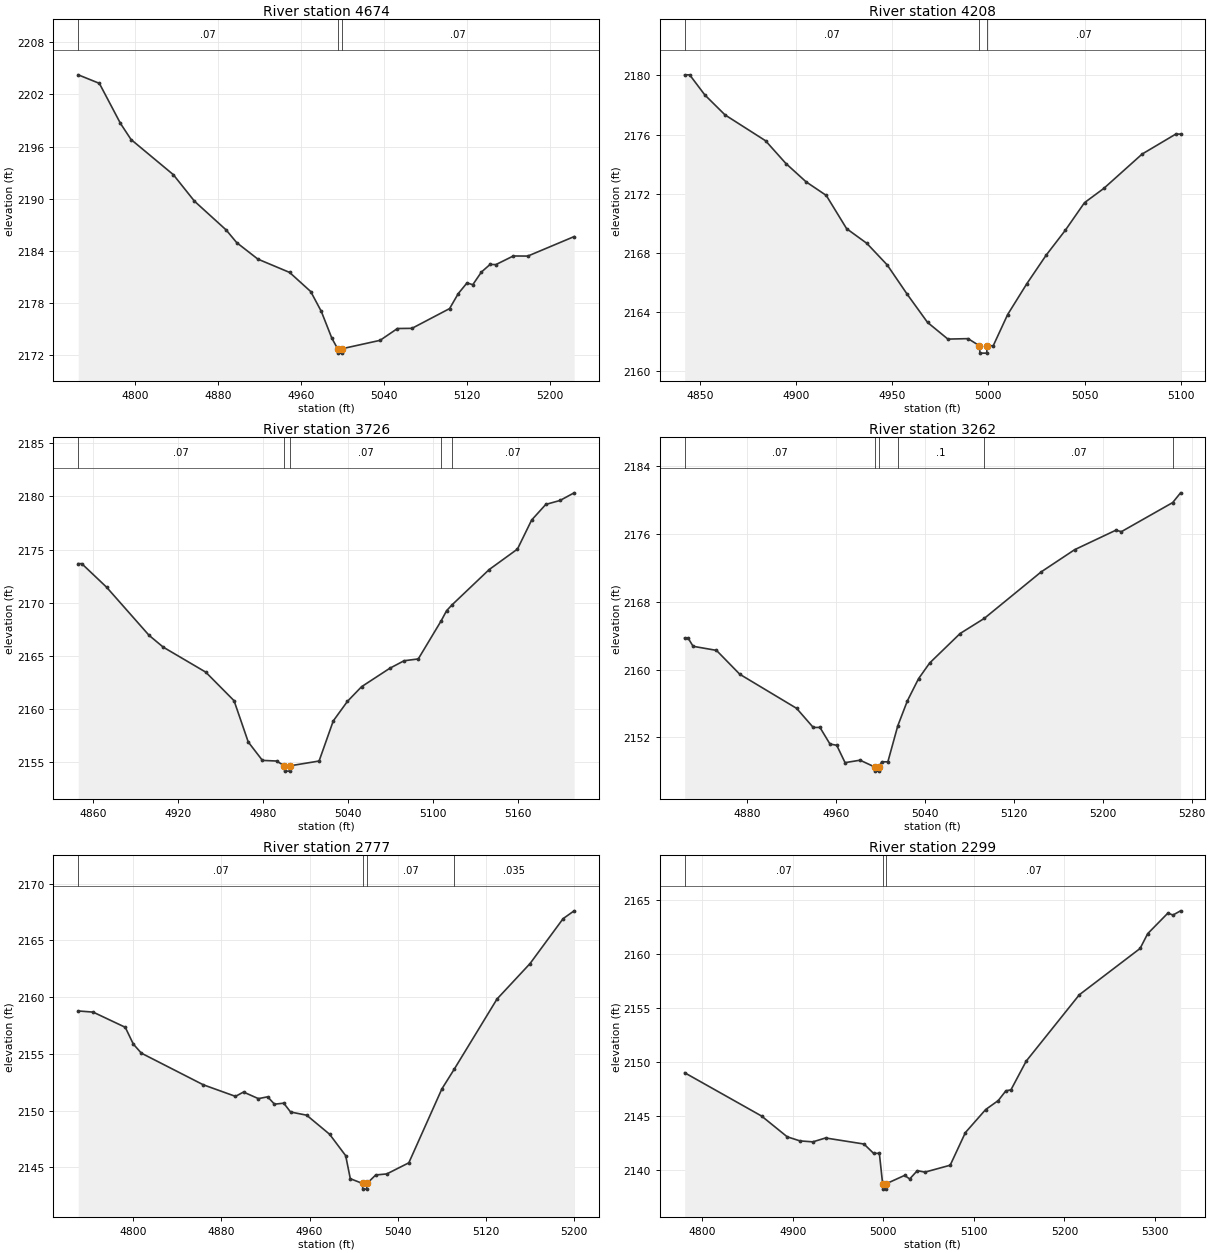
Type RM Length L Ch R = 1,4674,466,466,466
BEGIN DESCRIPTION:
Stream0244 10.0
END DESCRIPTION:
XS GIS Cut Line= 3
      1805375.01     13897325.03      1805325.00     13897075.00
      1805224.99     13896874.99
#Sta/Elev= 30
  4745.1 2204.25  4765.5 2203.27  4785.9 2198.66  4796.1 2196.81  4836.9 2192.77
  4857.3 2189.72  4887.9 2186.41  4898.1 2184.95  4918.5 2183.06  4949.1 2181.53
  4969.5 2179.33  4979.7 2177.05  4989.9 2173.96  4995.5 2172.75  4995.8 2172.25
  4999.3 2172.25  4999.5 2172.75  5036.4 2173.72  5053.2 2175.08  5067.2 2175.10
  5103.5 2177.37  5111.9 2179.10  5120.3 2180.32  5125.9 2180.12  5134.2 2181.57
  5142.6 2182.45  5148.2 2182.43  5165.0 2183.42  5179.0 2183.41  5223.7 2185.65
#Mann=3,-1,0
  4745.1    0.07       0  4995.5    0.05       0  4999.5    0.07       0
Bank Sta=4995.5,4999.5
Exp/Cntr=0.3,0.1

Type RM Length L Ch R = 1,4208,482,482,482
BEGIN DESCRIPTION:
Stream0244 9.0
END DESCRIPTION:
XS GIS Cut Line= 3
      1805725.02     13897174.95      1805775.00     13897025.00
      1805775.00     13896924.96
#Sta/Elev= 29
  4841.9 2180.04  4844.5 2180.04  4852.4 2178.68  4862.9 2177.33  4884.0 2175.58
  4894.6 2174.04  4905.1 2172.80  4915.6 2171.88  4926.2 2169.63  4936.7 2168.64
  4947.3 2167.18  4957.8 2165.18  4968.3 2163.29  4978.9 2162.16  4989.4 2162.19
  4995.3 2161.71  4995.6 2161.21  4999.1 2161.21  4999.3 2161.71  5002.5 2161.71
  5010.0 2163.82  5020.0 2165.91  5030.0 2167.83  5040.0 2169.52  5050.0 2171.39
  5060.0 2172.35  5080.0 2174.68  5097.5 2176.03  5100.0 2176.03
#Mann=3,-1,0
  4841.9    0.07       0  4995.3    0.05       0  4999.3    0.07       0
Bank Sta=4995.3,4999.3
Exp/Cntr=0.3,0.1

Type RM Length L Ch R = 1,3726,464,464,464
BEGIN DESCRIPTION:
Stream0244 8.0
END DESCRIPTION:
XS GIS Cut Line= 3
      1806225.00     13897174.99      1806225.00     13897025.00
      1806225.00     13896824.99
#Sta/Elev= 30
  4849.7 2173.68  4852.2 2173.68  4869.7 2171.47  4899.7 2166.94  4909.7 2165.83
  4939.7 2163.48  4959.7 2160.79  4969.7 2156.91  4979.7 2155.18  4989.7 2155.12
  4995.2 2154.67  4995.4 2154.17  4998.9 2154.17  4999.2 2154.67  5019.7 2155.12
  5029.7 2158.89  5039.7 2160.73  5049.7 2162.11  5069.7 2163.85  5079.7 2164.55
  5089.7 2164.72  5105.8 2168.29  5109.7 2169.26  5113.5 2169.80  5139.7 2173.12
  5159.7 2175.05  5169.7 2177.78  5179.7 2179.25  5189.7 2179.62  5199.7 2180.34
#Mann=5,-1,0
  4849.7    0.07       0  4995.2    0.05       0  4999.2    0.07       0
  5105.8     0.1       0  5113.5    0.07       0
Bank Sta=4995.2,4999.2
Exp/Cntr=0.3,0.1

Type RM Length L Ch R = 1,3262,485,485,485
BEGIN DESCRIPTION:
Stream0244 7.0
END DESCRIPTION:
XS GIS Cut Line= 3
      1806574.98     13897125.04      1806675.00     13896975.00
      1806655.98     13896709.90
#Sta/Elev= 30
  4823.9 2163.73  4826.9 2163.73  4831.5 2162.74  4852.5 2162.26  4873.5 2159.44
  4924.6 2155.42  4939.6 2153.16  4945.6 2153.17  4954.6 2151.21  4960.7 2151.06
  4968.2 2149.01  4981.7 2149.30  4994.7 2148.51  4995.0 2148.01  4998.5 2148.01
  4998.7 2148.51  5001.2 2149.11  5006.7 2149.11  5015.6 2153.35  5024.3 2156.32
  5034.3 2158.92  5044.3 2160.77  5071.7 2164.25  5093.4 2166.03  5144.6 2171.52
  5174.7 2174.14  5211.8 2176.44  5216.8 2176.27  5262.9 2179.70  5270.0 2180.85
#Mann=6,-1,0
  4823.9    0.07       0  4994.7    0.05       0  4998.7    0.07       0
  5015.6     0.1       0  5093.4    0.07       0  5262.9   0.035       0
Bank Sta=4994.7,4998.7
Exp/Cntr=0.3,0.1

Type RM Length L Ch R = 1,2777,478,478,478
BEGIN DESCRIPTION:
Stream0244 6.0
END DESCRIPTION:
XS GIS Cut Line= 3
      1806975.00     13897275.00      1807125.00     13897075.00
      1807125.00     13896874.99
#Sta/Elev= 30
  4750.1 2158.78  4763.6 2158.68  4792.8 2157.34  4800.1 2155.86  4807.4 2155.06
  4863.6 2152.27  4892.8 2151.25  4900.1 2151.63  4913.6 2151.05  4922.0 2151.21
  4928.2 2150.56  4936.6 2150.65  4942.8 2149.87  4957.4 2149.59  4978.2 2147.91
  4992.8 2146.02  4997.0 2143.99  5008.1 2143.57  5008.3 2143.07  5011.8 2143.07
  5012.1 2143.57  5020.1 2144.32  5030.1 2144.41  5050.1 2145.39  5080.1 2151.91
  5091.2 2153.63  5130.1 2159.83  5160.1 2162.96  5190.1 2166.92  5200.1 2167.61
#Mann=4,-1,0
  4750.1    0.07       0  5008.1    0.05       0  5012.1    0.07       0
  5091.2   0.035       0
Bank Sta=5008.1,5012.1
Exp/Cntr=0.3,0.1

Type RM Length L Ch R = 1,2299,436,436,436
BEGIN DESCRIPTION:
Stream0244 5.0
END DESCRIPTION:
XS GIS Cut Line= 3
      1807424.97     13897325.03      1807575.00     13897175.00
      1807425.00     13896874.99
#Sta/Elev= 30
  4780.7 2149.00  4865.6 2145.00  4893.9 2143.08  4908.0 2142.70  4922.2 2142.61
  4936.3 2142.97  4978.7 2142.41  4989.3 2141.55  4995.7 2141.55  4999.3 2138.74
  4999.5 2138.24  5003.0 2138.24  5003.3 2138.74  5023.6 2139.51  5029.2 2139.18
  5037.6 2139.95  5046.0 2139.81  5073.9 2140.45  5090.7 2143.47  5113.1 2145.60
  5127.0 2146.43  5135.4 2147.33  5141.0 2147.42  5157.8 2150.07  5216.5 2156.21
  5283.6 2160.49  5292.0 2161.86  5314.3 2163.76  5319.9 2163.58  5328.3 2163.97
#Mann=3,-1,0
  4780.7    0.07       0  4999.3    0.05       0  5003.3    0.07       0
Bank Sta=4999.3,5003.3
Exp/Cntr=0.3,0.1

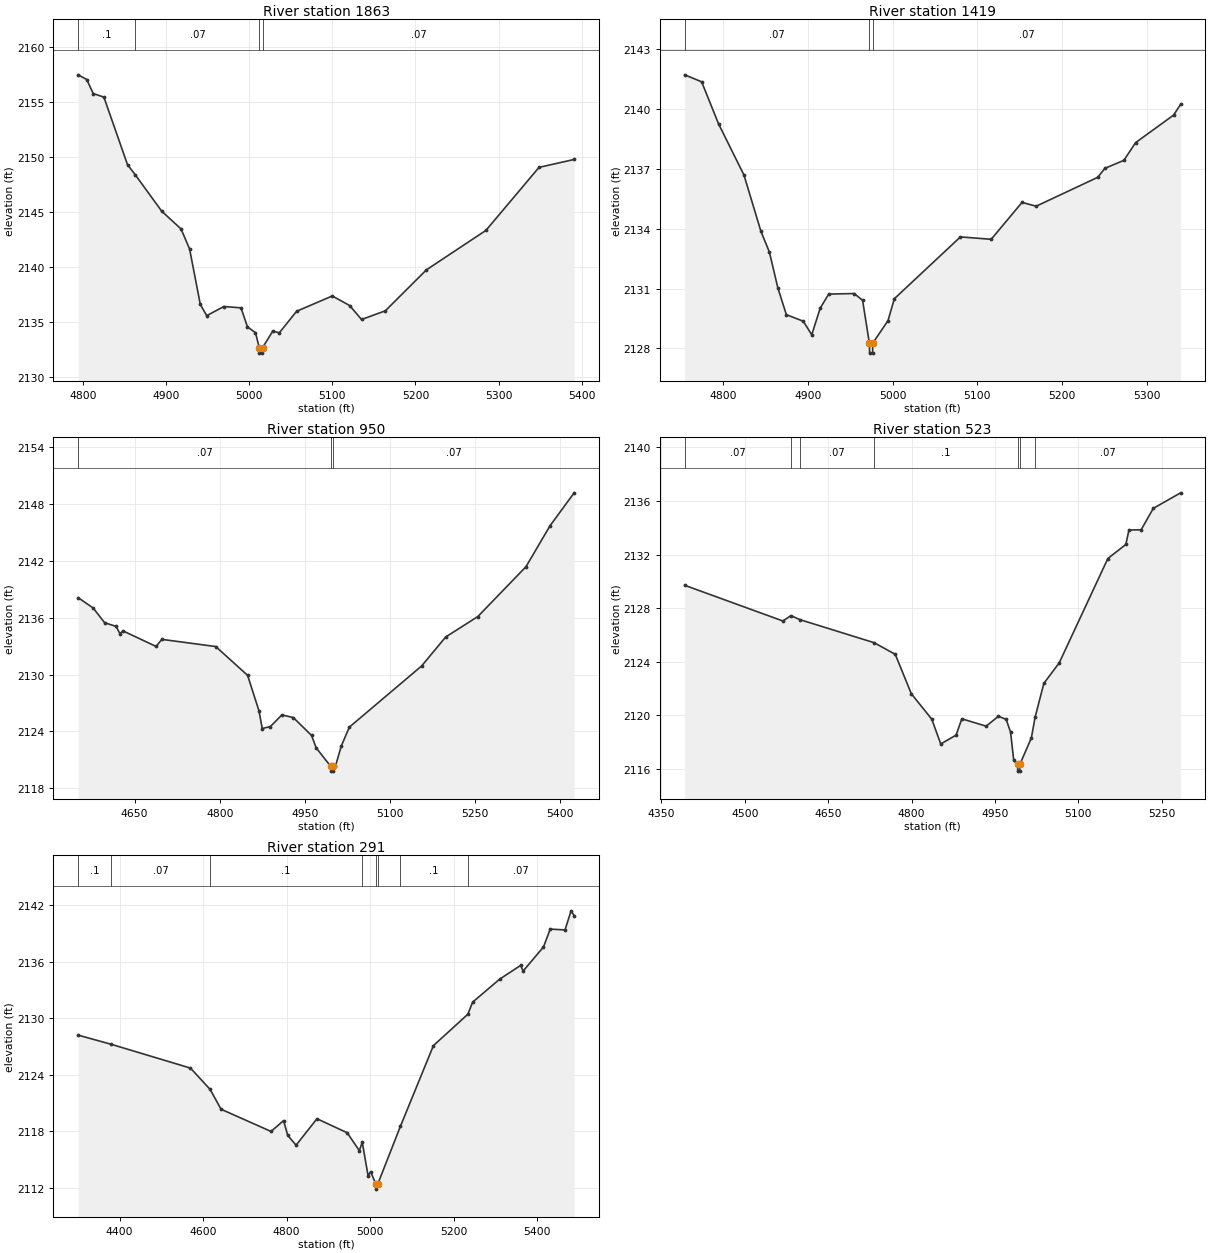
Type RM Length L Ch R = 1,1863,444,444,444
BEGIN DESCRIPTION:
Stream0244 4.0
END DESCRIPTION:
XS GIS Cut Line= 3
      1808025.00     13897375.00      1807975.00     13897175.00
      1807674.98     13896924.98
#Sta/Elev= 30
  4794.2 2157.50  4804.5 2157.07  4812.2 2155.80  4825.1 2155.47  4853.5 2149.33
  4863.1 2148.38  4894.7 2145.09  4917.9 2143.48  4928.2 2141.66  4941.1 2136.61
  4948.8 2135.59  4969.4 2136.42  4990.1 2136.30  4997.8 2134.57  5007.5 2134.04
  5012.0 2132.68  5012.3 2132.18  5015.8 2132.18  5016.0 2132.68  5028.3 2134.18
  5036.2 2134.03  5057.0 2135.99  5099.9 2137.38  5120.8 2136.51  5135.1 2135.24
  5163.7 2136.03  5213.2 2139.76  5284.8 2143.35  5348.6 2149.08  5390.9 2149.80
#Mann=4,-1,0
  4794.2     0.1       0  4863.1    0.07       0  5012.0    0.05       0
  5016.0    0.07       0
Bank Sta=5012,5016
Exp/Cntr=0.3,0.1

Type RM Length L Ch R = 1,1419,469,469,469
BEGIN DESCRIPTION:
Stream0244 3.0
END DESCRIPTION:
XS GIS Cut Line= 3
      1808275.00     13897125.03      1808275.00     13896875.00
      1807975.03     13896725.02
#Sta/Elev= 30
  4754.5 2141.72  4774.5 2141.37  4794.5 2139.26  4824.5 2136.69  4844.5 2133.87
  4854.5 2132.83  4864.5 2131.03  4874.5 2129.69  4894.5 2129.36  4904.5 2128.68
  4914.5 2130.02  4924.5 2130.72  4954.5 2130.75  4964.5 2130.41  4972.5 2128.26
  4972.8 2127.76  4976.3 2127.76  4976.5 2128.26  4994.5 2129.39  5002.0 2130.49
  5080.0 2133.59  5116.3 2133.47  5152.7 2135.32  5169.4 2135.13  5242.1 2136.58
  5250.5 2137.03  5272.9 2137.43  5286.8 2138.32  5331.6 2139.70  5339.9 2140.24
#Mann=3,-1,0
  4754.5    0.07       0  4972.5    0.05       0  4976.5    0.07       0
Bank Sta=4972.5,4976.5
Exp/Cntr=0.3,0.1

Type RM Length L Ch R = 1,950,427,427,427
BEGIN DESCRIPTION:
Stream0244 2.0
END DESCRIPTION:
XS GIS Cut Line= 3
      1808729.10     13897121.18      1808675.00     13896675.00
      1808375.01     13896375.01
#Sta/Elev= 30
  4550.6 2138.13  4577.0 2137.04  4597.1 2135.49  4617.3 2135.10  4624.2 2134.32
  4629.3 2134.63  4687.8 2132.98  4697.9 2133.73  4792.9 2132.97  4849.0 2129.93
  4869.1 2126.17  4874.8 2124.31  4889.2 2124.52  4909.4 2125.75  4929.5 2125.47
  4961.7 2123.58  4969.8 2122.27  4995.5 2120.31  4995.8 2119.81  4999.3 2119.81
  4999.5 2120.31  5003.6 2120.31  5014.2 2122.48  5028.3 2124.46  5155.6 2130.92
  5198.0 2133.98  5254.6 2136.14  5339.5 2141.41  5381.9 2145.74  5424.3 2149.21
#Mann=3,-1,0
  4550.6    0.07       0  4995.5    0.05       0  4999.5    0.07       0
Bank Sta=4995.5,4999.5
Exp/Cntr=0.3,0.1

Type RM Length L Ch R = 1,523,232,232,232
BEGIN DESCRIPTION:
Stream0244 1.0
END DESCRIPTION:
XS GIS Cut Line= 3
      1808911.77     13896915.92      1809087.57     13896622.95
      1808825.44     13896138.94
#Sta/Elev= 30
  4391.9 2129.70  4568.6 2127.03  4582.9 2127.43  4599.4 2127.13  4732.6 2125.41
  4770.7 2124.54  4799.5 2121.60  4836.4 2119.69  4852.5 2117.84  4880.1 2118.50
  4890.4 2119.72  4934.3 2119.17  4956.2 2119.91  4970.1 2119.68  4978.1 2118.73
  4983.8 2116.61  4990.8 2116.31  4991.0 2115.81  4994.5 2115.81  4994.8 2116.31
  5015.5 2118.29  5022.2 2119.83  5038.0 2122.37  5065.6 2123.90  5153.1 2131.70
  5185.4 2132.75  5191.1 2133.83  5213.0 2133.85  5234.9 2135.45  5284.0 2136.61
#Mann=7,-1,0
  4391.9    0.07       0  4582.9     0.1       0  4599.4    0.07       0
  4732.6     0.1       0  4990.8    0.05       0  4994.8     0.1       0
  5022.2    0.07       0
Bank Sta=4990.8,4994.8
Exp/Cntr=0.3,0.1

Type RM Length L Ch R = 1,291,0,0,0
BEGIN DESCRIPTION:
Stream0244 0.0
END DESCRIPTION:
XS GIS Cut Line= 4
      1809004.25     13896857.31      1809203.09     13896481.05
      1809204.51     13896306.16      1808733.40     13895956.26
#Sta/Elev= 30
  4301.0 2128.22  4379.1 2127.26  4569.8 2124.72  4616.9 2122.45  4642.9 2120.35
  4762.6 2117.99  4792.6 2119.14  4802.6 2117.57  4822.6 2116.53  4872.6 2119.34
  4944.9 2117.85  4974.1 2115.95  4981.0 2116.85  4995.0 2113.28  5001.2 2113.71
  5013.8 2112.36  5014.1 2111.86  5017.8 2112.36  5072.5 2118.55  5151.4 2127.11
  5233.8 2130.44  5245.3 2131.73  5310.0 2134.17  5360.1 2135.63  5366.3 2135.04
  5414.9 2137.59  5431.0 2139.49  5466.4 2139.40  5481.0 2141.43  5488.3 2140.92
#Mann=8,-1,0
  4301.0     0.1       0  4379.1    0.07       0  4616.9     0.1       0
  4981.0    0.07       0  5013.8    0.05       0  5017.8    0.07       0
  5072.5     0.1       0  5233.8    0.07       0
Bank Sta=5013.8,5017.8
Exp/Cntr=0.3,0.1

Chan Stop Cuts=-1