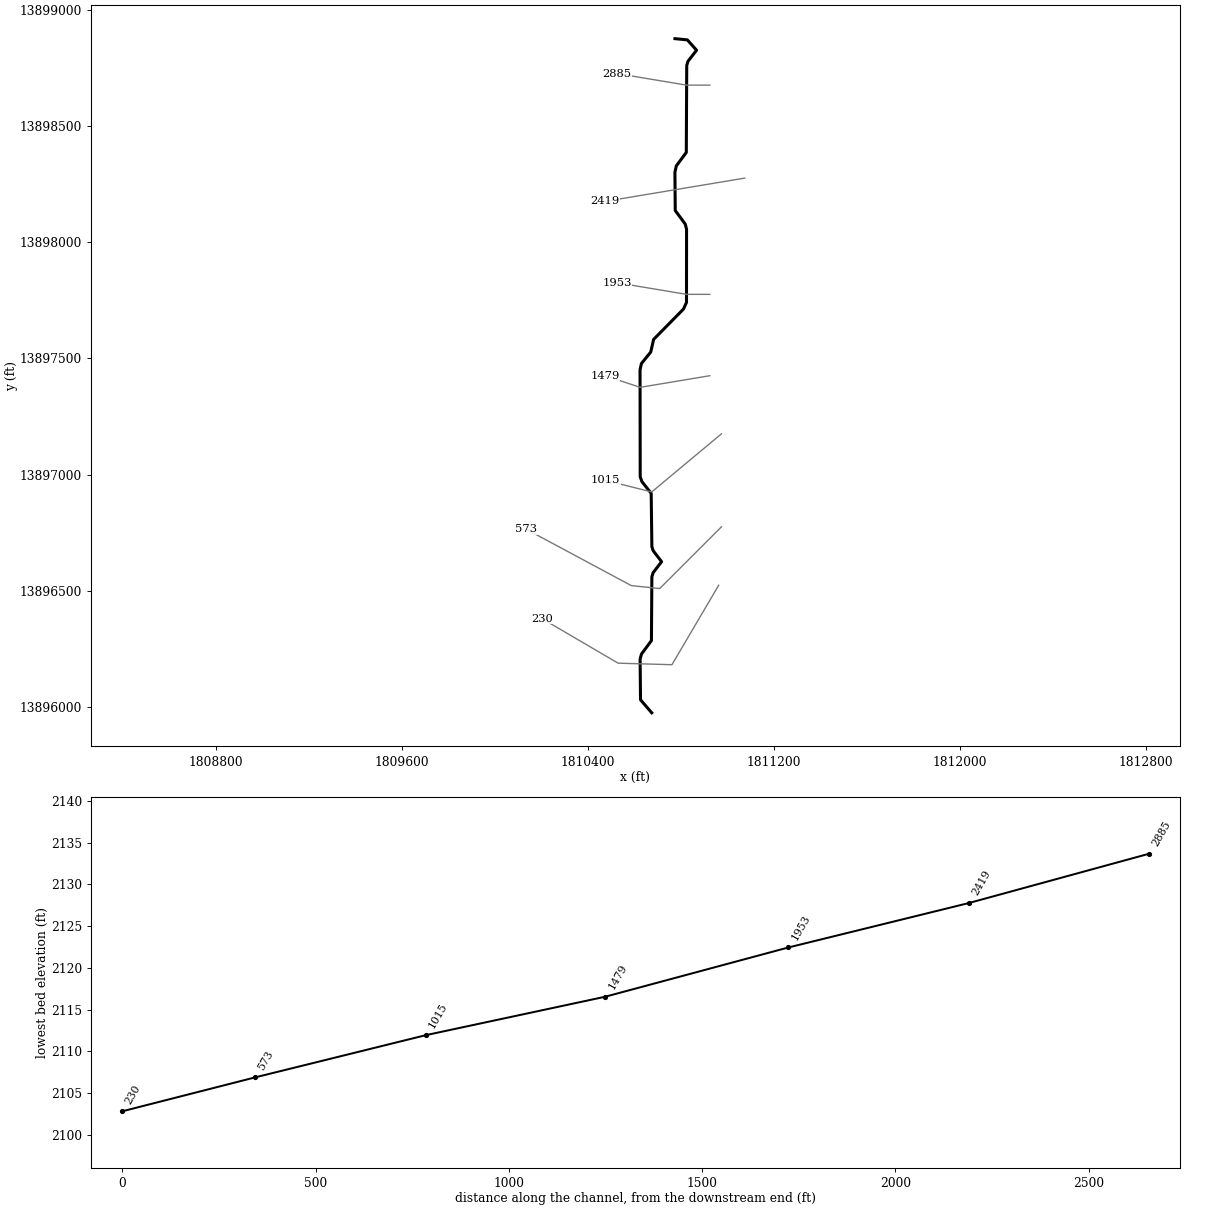
--- Stream0245.prj (project) ---

Proj Title=Stream0245 Base Level Engineering
Current Plan=p01
Default Exp/Contr=0.3,0.1
English Units
Geom File=g01
Flow File=f01
Plan File=p01
BEGIN DESCRIPTION:
Stream0245
END DESCRIPTION:

--- Stream0245.p01 (plan) ---

Plan Title=Multiple Run
Short Identifier=Multiple
Geom File=g01
Flow File=f01
Subcritical Flow
K Sum by GR= 0
Std Step Tol= 0.01
Critical Tol= 0.01
Num of Std Step Trials= 20
Max Error Tol= 0.3
Flow Tol Ratio= 0.001
Split Flow NTrial= 30
Split Flow Tol= 0.02
Split Flow Ratio= 0.02
Log Output Level= 0
Friction Slope Method= 1
Unsteady Friction Slope Method= 2
Unsteady Bridges Friction Slope Method= 1
Parabolic Critical Depth
Global Vel Dist=  1 , 1 , 1
Global Log Level= 0
CheckData=True
Encroach Param= -1, 0, 0, 0
BEGIN DESCRIPTION:
Multiple Run
END DESCRIPTION:

--- Stream0245.f01 (steady flow) ---

Flow Title=Multiple
Number of Profiles=7
Profile Names=10-year,25-year,50-year,1pct_min,100-year,1pct_plu,500-year
River Rch & RM= Stream0245,Reach-1,2885
     850    1439    1994    1336    2666    5320    4714
Boundary for River Rch & Prof#=Stream0245,Reach-1,1
Up Type=0
Dn Type=3
Dn Slope=0.005
Boundary for River Rch & Prof#=Stream0245,Reach-1,2
Up Type=0
Dn Type=3
Dn Slope=0.005
Boundary for River Rch & Prof#=Stream0245,Reach-1,3
Up Type=0
Dn Type=3
Dn Slope=0.005
Boundary for River Rch & Prof#=Stream0245,Reach-1,4
Up Type=0
Dn Type=3
Dn Slope=0.005
Boundary for River Rch & Prof#=Stream0245,Reach-1,5
Up Type=0
Dn Type=3
Dn Slope=0.005
Boundary for River Rch & Prof#=Stream0245,Reach-1,6
Up Type=0
Dn Type=3
Dn Slope=0.005
Boundary for River Rch & Prof#=Stream0245,Reach-1,7
Up Type=0
Dn Type=3
Dn Slope=0.005

--- Stream0245.g01 (geometry) ---

Geom Title=Existing Conditions

River Reach=Stream0245,Reach-1
Reach XY= 30
      1810775.00     13898875.00      1810828.35     13898869.70
      1810867.92     13898825.27      1810831.01     13898777.47
      1810825.66     13898759.85      1810823.78     13898385.50
      1810780.75     13898327.33      1810774.80     13898300.08
      1810776.22     13898135.51      1810819.25     13898077.33
      1810824.93     13898054.97      1810824.62     13897740.16
      1810811.63     13897711.68      1810683.14     13897581.06
      1810670.78     13897526.75      1810630.71     13897477.35
      1810624.79     13897450.09      1810625.52     13896990.22
      1810633.14     13896968.94      1810672.74     13896919.06
      1810675.66     13896690.16      1810681.02     13896672.55
      1810717.44     13896625.00      1810681.02     13896577.45
      1810675.66     13896559.84      1810673.78     13896285.50
      1810630.75     13896227.33      1810625.07     13896204.97
      1810626.89     13896030.78      1810675.00     13895975.00

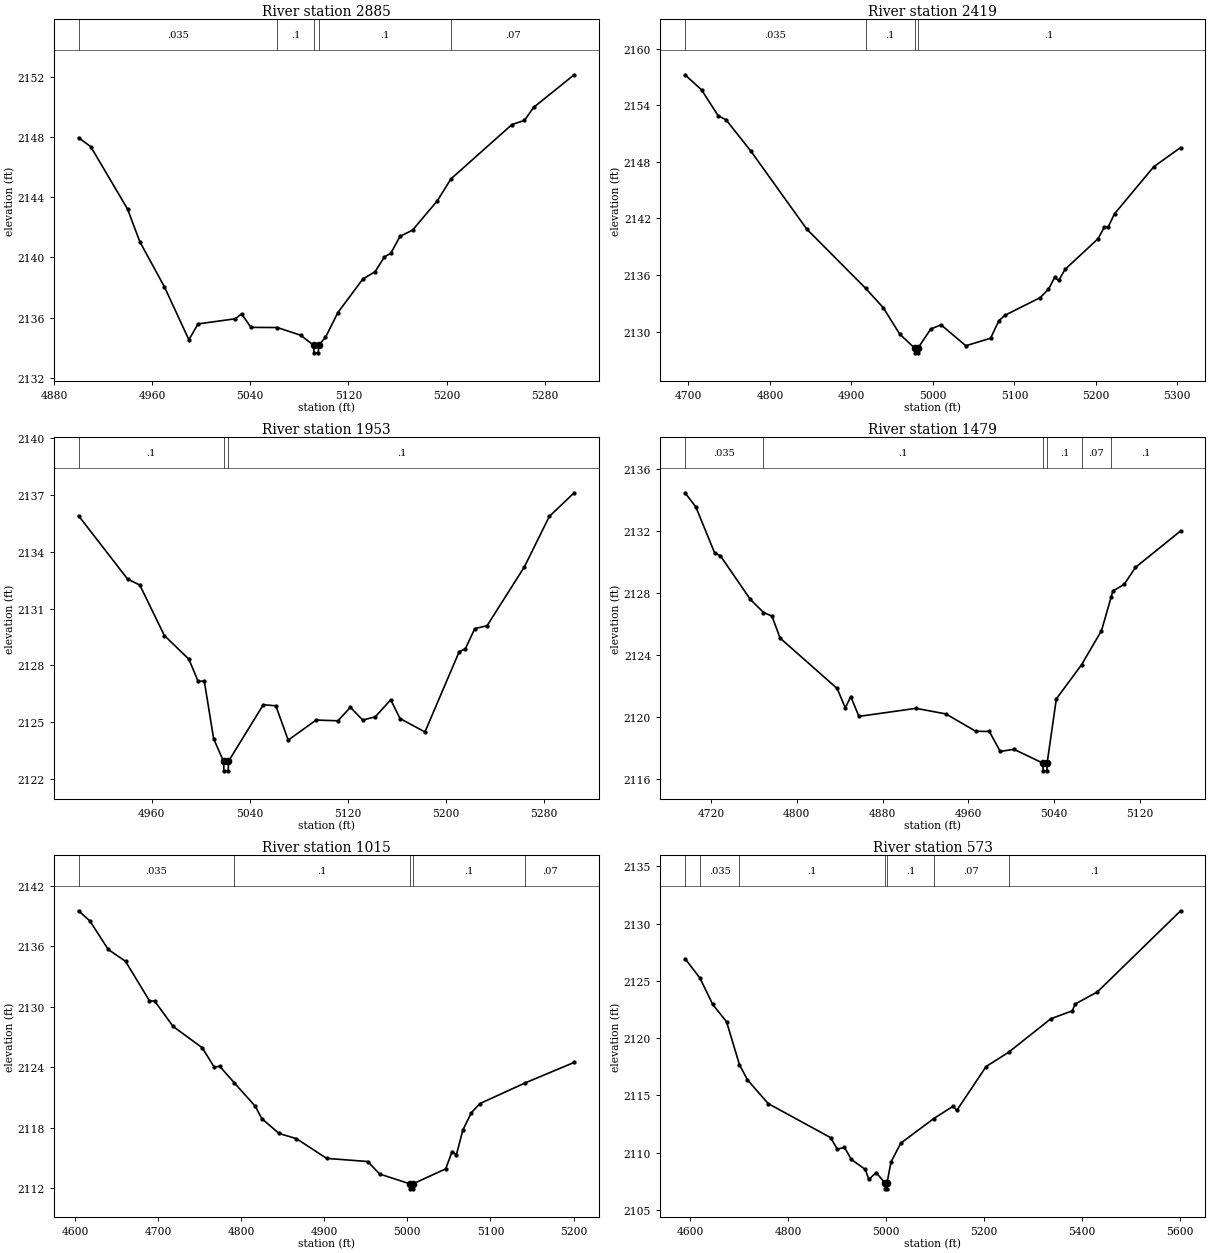
Type RM Length L Ch R = 1,2885,466,466,466
BEGIN DESCRIPTION:
Stream0245 6.0
END DESCRIPTION:
XS GIS Cut Line= 3
      1810925.01     13898675.00      1810825.00     13898675.00
      1810524.95     13898725.01
#Sta/Elev= 30
  4899.9 2147.95  4909.9 2147.35  4939.9 2143.21  4949.9 2141.04  4969.9 2138.06
  4989.9 2134.54  4997.4 2135.59  5027.8 2135.93  5032.9 2136.26  5040.5 2135.36
  5061.9 2135.35  5081.0 2134.84  5091.7 2134.17  5091.9 2133.67  5095.4 2133.67
  5095.7 2134.17  5101.3 2134.70  5111.4 2136.34  5131.7 2138.56  5141.8 2139.06
  5149.4 2140.04  5154.5 2140.27  5162.1 2141.40  5172.3 2141.81  5192.5 2143.76
  5203.7 2145.22  5253.4 2148.82  5263.5 2149.09  5271.1 2149.96  5304.1 2152.12
#Mann=5,-1,0
  4899.9   0.035       0  5061.9     0.1       0  5091.7   0.035       0
  5095.7     0.1       0  5203.7    0.07       0
Bank Sta=5091.7,5095.7
Exp/Cntr=0.3,0.1

Type RM Length L Ch R = 1,2419,466,466,466
BEGIN DESCRIPTION:
Stream0245 5.0
END DESCRIPTION:
XS GIS Cut Line= 3
      1811075.01     13898275.00      1810775.00     13898225.00
      1810474.98     13898175.00
#Sta/Elev= 30
  4695.7 2157.23  4716.0 2155.64  4736.3 2152.91  4746.4 2152.43  4776.8 2149.11
  4845.2 2140.87  4917.3 2134.61  4939.0 2132.55  4959.3 2129.74  4977.6 2128.26
  4977.8 2127.76  4981.3 2127.76  4981.6 2128.26  4997.3 2130.28  5010.0 2130.73
  5040.4 2128.51  5070.8 2129.31  5080.9 2131.16  5088.6 2131.75  5131.6 2133.61
  5141.8 2134.50  5149.4 2135.75  5154.4 2135.43  5162.1 2136.60  5202.6 2139.85
  5210.2 2141.05  5215.3 2141.14  5222.9 2142.50  5271.0 2147.48  5304.0 2149.52
#Mann=4,-1,0
  4695.7   0.035       0  4917.3     0.1       0  4977.6    0.05       0
  4981.6     0.1       0
Bank Sta=4977.6,4981.6
Exp/Cntr=0.3,0.1

Type RM Length L Ch R = 1,1953,474,474,474
BEGIN DESCRIPTION:
Stream0245 4.0
END DESCRIPTION:
XS GIS Cut Line= 3
      1810925.03     13897775.00      1810825.00     13897775.00
      1810524.96     13897825.01
#Sta/Elev= 30
  4900.4 2135.90  4940.4 2132.56  4950.4 2132.24  4970.4 2129.58  4990.4 2128.33
  4997.9 2127.17  5003.0 2127.17  5010.6 2124.13  5018.7 2122.94  5019.0 2122.44
  5022.5 2122.44  5022.7 2122.94  5051.1 2125.93  5061.3 2125.87  5071.4 2124.06
  5094.2 2125.12  5111.9 2125.08  5122.1 2125.79  5132.2 2125.12  5142.4 2125.29
  5155.0 2126.19  5162.6 2125.20  5182.9 2124.49  5210.8 2128.72  5215.9 2128.88
  5223.5 2129.94  5233.6 2130.10  5264.0 2133.20  5284.3 2135.86  5304.6 2137.11
#Mann=3,-1,0
  4900.4     0.1       0  5018.7    0.05       0  5022.7     0.1       0
Bank Sta=5018.7,5022.7
Exp/Cntr=0.3,0.1

Type RM Length L Ch R = 1,1479,464,464,464
BEGIN DESCRIPTION:
Stream0245 3.0
END DESCRIPTION:
XS GIS Cut Line= 3
      1810924.96     13897424.99      1810625.00     13897375.00
      1810475.01     13897425.00
#Sta/Elev= 30
  4695.8 2134.46  4705.9 2133.55  4723.6 2130.56  4728.7 2130.41  4756.6 2127.60
  4769.0 2126.74  4776.9 2126.51  4784.5 2125.09  4837.7 2121.84  4845.3 2120.59
  4850.4 2121.32  4858.0 2120.04  4911.2 2120.56  4939.1 2120.20  4967.0 2119.08
  4979.6 2119.07  4989.8 2117.78  5002.5 2117.92  5029.5 2117.03  5029.8 2116.53
  5033.3 2116.53  5033.5 2117.03  5042.1 2121.17  5065.6 2123.37  5084.2 2125.57
  5093.1 2127.71  5094.8 2128.12  5105.3 2128.55  5115.9 2129.65  5158.0 2132.00
#Mann=6,-1,0
  4695.8   0.035       0  4769.0     0.1       0  5029.5    0.05       0
  5033.5     0.1       0  5065.6    0.07       0  5093.1     0.1       0
Bank Sta=5029.5,5033.5
Exp/Cntr=0.3,0.1

Type RM Length L Ch R = 1,1015,442,442,442
BEGIN DESCRIPTION:
Stream0245 2.0
END DESCRIPTION:
XS GIS Cut Line= 3
      1810975.00     13897175.00      1810675.00     13896925.00
      1810474.97     13896975.01
#Sta/Elev= 30
  4604.1 2139.50  4617.8 2138.49  4639.9 2135.66  4660.7 2134.49  4689.4 2130.59
  4695.9 2130.53  4718.0 2128.03  4753.1 2125.91  4767.5 2123.98  4774.0 2124.09
  4791.6 2122.44  4816.9 2120.11  4824.7 2118.89  4845.6 2117.41  4866.4 2116.90
  4902.8 2114.94  4952.3 2114.63  4966.6 2113.39  5002.9 2112.42  5003.2 2111.92
  5006.7 2111.92  5006.9 2112.42  5046.1 2113.90  5053.9 2115.62  5059.0 2115.29
  5066.8 2117.75  5077.1 2119.48  5087.4 2120.38  5142.2 2122.44  5200.8 2124.46
#Mann=5,-1,0
  4604.1   0.035       0  4791.6     0.1       0  5002.9    0.05       0
  5006.9     0.1       0  5142.2    0.07       0
Bank Sta=5002.9,5006.9
Exp/Cntr=0.3,0.1

Type RM Length L Ch R = 1,573,343,343,343
BEGIN DESCRIPTION:
Stream0245 1.0
END DESCRIPTION:
XS GIS Cut Line= 4
      1810975.01     13896775.01      1810709.39     13896509.39
      1810587.09     13896522.15      1810135.27     13896764.46
#Sta/Elev= 30
  4589.5 2126.94  4620.1 2125.24  4646.1 2122.94  4674.4 2121.42  4700.6 2117.69
  4716.8 2116.37  4759.2 2114.29  4886.5 2111.32  4900.6 2110.30  4914.8 2110.48
  4928.9 2109.41  4957.2 2108.55  4964.7 2107.67  4979.6 2108.27  4997.7 2107.35
  4998.0 2106.85  5001.5 2106.85  5001.7 2107.35  5009.8 2109.19  5029.9 2110.84
  5097.1 2112.98  5135.9 2114.04  5144.3 2113.71  5203.9 2117.52  5249.6 2118.76
  5336.0 2121.69  5379.8 2122.38  5385.5 2122.97  5430.9 2124.03  5600.8 2131.11
#Mann=7,-1,0
  4589.5     0.1       0  4620.1   0.035       0  4700.6     0.1       0
  4997.7    0.05       0  5001.7     0.1       0  5097.1    0.07       0
  5249.6     0.1       0
Bank Sta=4997.7,5001.7
Exp/Cntr=0.3,0.1

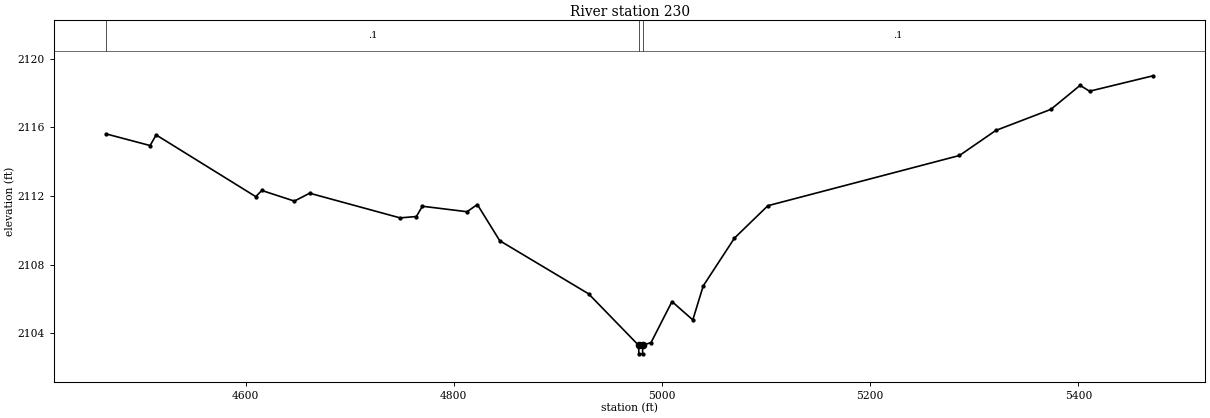
Type RM Length L Ch R = 1,230,0,0,0
BEGIN DESCRIPTION:
Stream0245 0.0
END DESCRIPTION:
XS GIS Cut Line= 4
      1810963.14     13896523.59      1810762.06     13896181.83
      1810530.58     13896188.41      1810204.48     13896379.16
#Sta/Elev= 30
  4465.9 2115.62  4508.2 2114.94  4514.0 2115.56  4609.7 2111.96  4615.5 2112.32
  4646.8 2111.70  4661.5 2112.16  4748.4 2110.72  4764.0 2110.80  4769.8 2111.40
  4812.7 2111.08  4822.6 2111.50  4844.1 2109.39  4929.5 2106.29  4977.5 2103.29
  4977.8 2102.79  4981.3 2102.79  4981.5 2103.29  4989.5 2103.45  5009.6 2105.84
  5029.6 2104.77  5039.6 2106.75  5069.6 2109.54  5101.7 2111.43  5285.8 2114.36
  5320.7 2115.82  5373.6 2117.05  5401.7 2118.45  5410.8 2118.11  5471.8 2119.01
#Mann=3,-1,0
  4465.9     0.1       0  4977.5    0.05       0  4981.5     0.1       0
Bank Sta=4977.5,4981.5
Exp/Cntr=0.3,0.1

Chan Stop Cuts=-1