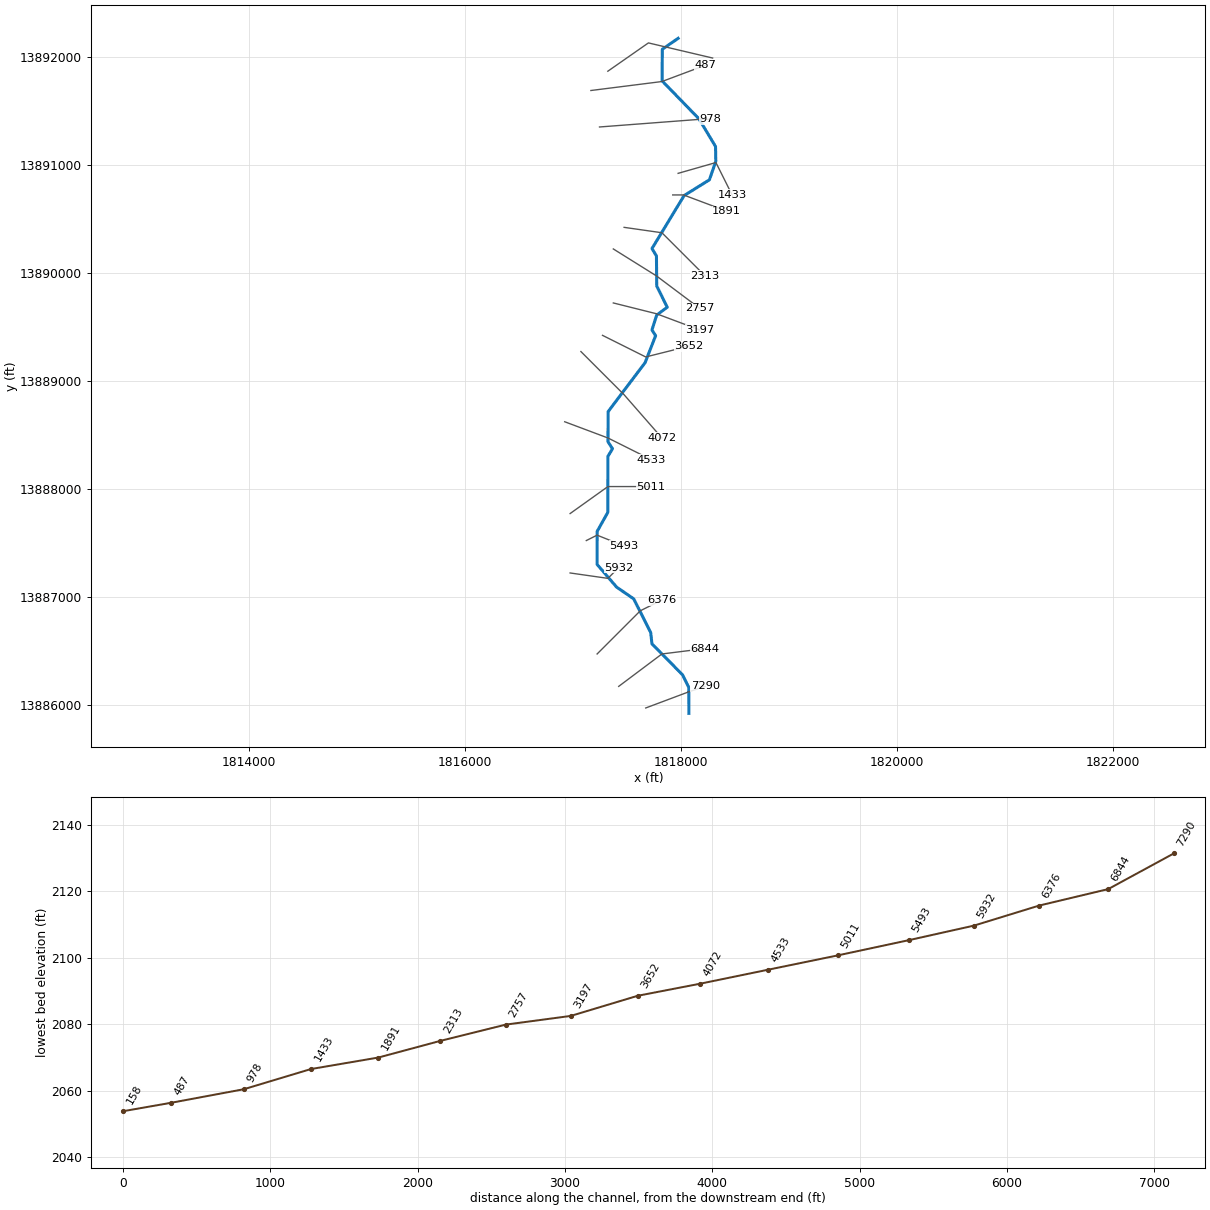
--- Stream0249.prj (project) ---

Proj Title=Stream0249 Base Level Engineering
Current Plan=p01
Default Exp/Contr=0.3,0.1
English Units
Geom File=g01
Flow File=f01
Plan File=p01
BEGIN DESCRIPTION:
Stream0249
END DESCRIPTION:

--- Stream0249.p01 (plan) ---

Plan Title=Multiple Run
Short Identifier=Multiple
Geom File=g01
Flow File=f01
Subcritical Flow
K Sum by GR= 0
Std Step Tol= 0.01
Critical Tol= 0.01
Num of Std Step Trials= 20
Max Error Tol= 0.3
Flow Tol Ratio= 0.001
Split Flow NTrial= 30
Split Flow Tol= 0.02
Split Flow Ratio= 0.02
Log Output Level= 0
Friction Slope Method= 1
Unsteady Friction Slope Method= 2
Unsteady Bridges Friction Slope Method= 1
Parabolic Critical Depth
Global Vel Dist=  1 , 1 , 1
Global Log Level= 0
CheckData=True
Encroach Param= -1, 0, 0, 0
BEGIN DESCRIPTION:
Multiple Run
END DESCRIPTION:

--- Stream0249.f01 (steady flow) ---

Flow Title=Multiple
Number of Profiles=7
Profile Names=10-year,25-year,50-year,1pct_min,100-year,1pct_plu,500-year
River Rch & RM= Stream0249,Reach-1,7290
    1872    3297    4693    3222    6428   12825   11934
River Rch & RM= Stream0249,Reach-1,978
    2097    3714    5306    3654    7290   14545   13621
Boundary for River Rch & Prof#=Stream0249,Reach-1,1
Up Type=0
Dn Type=3
Dn Slope=0.005
Boundary for River Rch & Prof#=Stream0249,Reach-1,2
Up Type=0
Dn Type=3
Dn Slope=0.005
Boundary for River Rch & Prof#=Stream0249,Reach-1,3
Up Type=0
Dn Type=3
Dn Slope=0.005
Boundary for River Rch & Prof#=Stream0249,Reach-1,4
Up Type=0
Dn Type=3
Dn Slope=0.005
Boundary for River Rch & Prof#=Stream0249,Reach-1,5
Up Type=0
Dn Type=3
Dn Slope=0.005
Boundary for River Rch & Prof#=Stream0249,Reach-1,6
Up Type=0
Dn Type=3
Dn Slope=0.005
Boundary for River Rch & Prof#=Stream0249,Reach-1,7
Up Type=0
Dn Type=3
Dn Slope=0.005

--- Stream0249.g01 (geometry) ---

Geom Title=Existing Conditions

River Reach=Stream0249,Reach-1
Reach XY= 30
      1818075.00     13885925.00      1818073.80     13886164.50
      1818016.86     13886281.06      1817732.86     13886568.83
      1817721.17     13886673.41      1817564.24     13886984.70
      1817404.91     13887094.79      1817224.57     13887304.82
      1817225.51     13887609.79      1817323.80     13887785.50
      1817325.18     13888305.02      1817367.44     13888375.00
      1817325.66     13888440.16      1817327.06     13888719.15
      1817669.48     13889172.57      1817766.76     13889421.77
      1817732.79     13889474.91      1817776.76     13889613.12
      1817874.45     13889685.48      1817777.24     13889880.93
      1817774.34     13890159.84      1817733.04     13890228.32
      1818030.62     13890719.38      1818264.61     13890864.90
      1818323.80     13891035.51      1818321.46     13891173.53
      1818166.86     13891431.06      1817827.06     13891780.85
      1817828.52     13892073.55      1817975.00     13892175.00

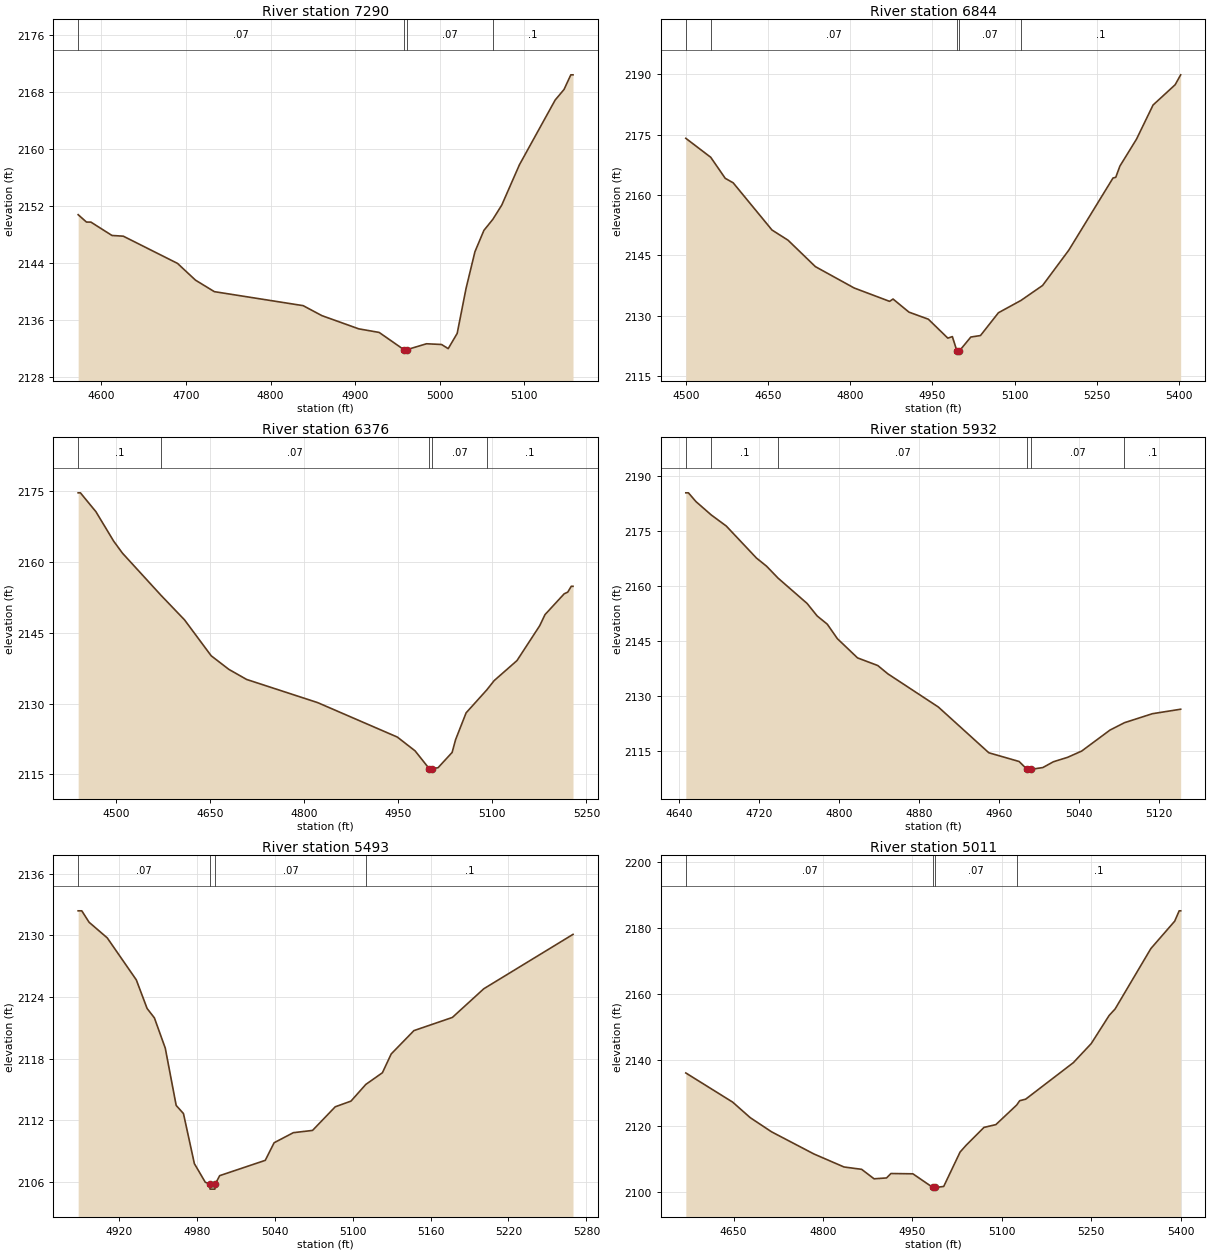
Type RM Length L Ch R = 1,7290,446,446,446
BEGIN DESCRIPTION:
Stream0249 16.0
END DESCRIPTION:
XS GIS Cut Line= 3
      1817675.03     13885975.01      1818075.00     13886125.00
      1818225.01     13886175.00
#Sta/Elev= 30
  4572.4 2150.80  4582.2 2149.77  4587.5 2149.76  4612.4 2147.89  4625.8 2147.79
  4689.9 2143.98  4711.2 2141.63  4733.5 2140.02  4838.5 2138.06  4860.7 2136.66
  4904.3 2134.81  4928.4 2134.31  4957.5 2131.91  4957.7 2131.41  4961.3 2131.41
  4961.6 2131.91  4984.4 2132.72  5002.2 2132.62  5010.1 2132.04  5020.7 2134.17
  5031.2 2140.48  5041.7 2145.61  5052.3 2148.60  5063.0 2150.17  5073.4 2152.14
  5094.4 2157.81  5136.6 2166.86  5147.1 2168.34  5155.1 2170.39  5157.7 2170.39
#Mann=4,-1,0
  4572.4    0.07       0  4957.5    0.05       0  4961.6    0.07       0
  5063.0     0.1       0
Bank Sta=4957.5,4961.6
Exp/Cntr=0.3,0.1

Type RM Length L Ch R = 1,6844,468,468,468
BEGIN DESCRIPTION:
Stream0249 15.0
END DESCRIPTION:
XS GIS Cut Line= 3
      1817424.97     13886174.98      1817825.00     13886475.00
      1818225.05     13886525.01
#Sta/Elev= 30
  4500.0 2174.06  4545.5 2169.34  4571.9 2164.12  4586.5 2162.99  4657.3 2151.26
  4686.5 2148.74  4736.5 2142.16  4807.3 2136.85  4871.9 2133.53  4878.2 2134.11
  4907.3 2130.85  4942.7 2129.09  4978.2 2124.39  4986.5 2124.77  4994.9 2121.16
  4995.1 2120.66  4999.0 2121.16  5020.2 2124.66  5037.8 2125.03  5070.6 2130.70
  5111.6 2133.75  5151.2 2137.48  5199.1 2146.27  5279.7 2164.19  5284.7 2164.36
  5292.3 2167.16  5322.5 2173.83  5352.8 2182.33  5393.1 2187.37  5403.2 2189.84
#Mann=5,-1,0
  4500.0     0.1       0  4545.5    0.07       0  4994.9    0.05       0
  4999.0    0.07       0  5111.6     0.1       0
Bank Sta=4994.9,4999
Exp/Cntr=0.3,0.1

Type RM Length L Ch R = 1,6376,444,444,444
BEGIN DESCRIPTION:
Stream0249 14.0
END DESCRIPTION:
XS GIS Cut Line= 3
      1817224.98     13886474.98      1817625.00     13886875.00
      1817824.98     13886974.99
#Sta/Elev= 30
  4439.3 2174.63  4442.9 2174.63  4467.6 2170.64  4495.9 2164.41  4510.0 2161.85
  4571.9 2152.87  4609.0 2147.73  4651.5 2140.13  4679.7 2137.25  4708.0 2135.12
  4821.2 2130.22  4948.4 2122.92  4976.7 2120.00  4999.4 2116.21  4999.7 2115.71
  5003.3 2115.71  5003.6 2116.21  5013.4 2116.44  5035.8 2119.67  5041.3 2122.37
  5058.1 2128.05  5091.3 2132.94  5102.8 2134.87  5139.2 2139.11  5175.5 2146.50
  5183.9 2148.84  5214.6 2153.26  5220.2 2153.60  5225.8 2154.84  5228.6 2154.84
#Mann=5,-1,0
  4439.3     0.1       0  4571.9    0.07       0  4999.4    0.05       0
  5003.6    0.07       0  5091.3     0.1       0
Bank Sta=4999.4,5003.6
Exp/Cntr=0.3,0.1

Type RM Length L Ch R = 1,5932,439,439,439
BEGIN DESCRIPTION:
Stream0249 13.0
END DESCRIPTION:
XS GIS Cut Line= 3
      1816974.97     13887225.00      1817325.00     13887175.00
      1817424.99     13887274.99
#Sta/Elev= 30
  4646.5 2185.32  4649.1 2185.32  4656.6 2182.95  4672.0 2179.29  4686.9 2176.31
  4717.2 2167.58  4727.3 2165.37  4738.7 2162.15  4767.8 2155.25  4777.9 2151.84
  4788.0 2149.61  4798.1 2145.67  4818.3 2140.44  4838.5 2138.37  4848.6 2136.11
  4899.1 2127.09  4949.6 2114.65  4979.9 2112.28  4987.8 2110.16  4988.1 2109.66
  4991.8 2109.66  4992.1 2110.16  5003.6 2110.63  5014.2 2112.21  5028.4 2113.41
  5042.5 2115.12  5070.8 2120.82  5085.3 2122.83  5113.2 2125.27  5141.5 2126.49
#Mann=6,-1,0
  4646.5    0.07       0  4672.0     0.1       0  4738.7    0.07       0
  4987.8    0.05       0  4992.1    0.07       0  5085.3     0.1       0
Bank Sta=4987.8,4992.1
Exp/Cntr=0.3,0.1

Type RM Length L Ch R = 1,5493,482,482,482
BEGIN DESCRIPTION:
Stream0249 12.0
END DESCRIPTION:
XS GIS Cut Line= 3
      1817124.97     13887524.99      1817225.00     13887575.00
      1817475.01     13887475.00
#Sta/Elev= 30
  4888.6 2132.38  4891.4 2132.38  4897.0 2131.27  4911.0 2129.75  4933.4 2125.66
  4941.7 2122.88  4947.3 2121.97  4955.7 2119.02  4964.1 2113.45  4969.7 2112.66
  4978.1 2107.79  4986.5 2105.98  4989.9 2105.81  4990.2 2105.31  4993.9 2105.31
  4994.2 2105.81  4997.6 2106.62  5032.7 2108.11  5039.5 2109.82  5054.3 2110.80
  5069.1 2111.02  5086.6 2113.32  5098.7 2113.87  5110.1 2115.49  5122.9 2116.63
  5129.7 2118.46  5147.2 2120.73  5176.8 2122.01  5201.0 2124.80  5269.7 2130.09
#Mann=4,-1,0
  4888.6    0.07       0  4989.9    0.05       0  4994.2    0.07       0
  5110.1     0.1       0
Bank Sta=4989.9,4994.2
Exp/Cntr=0.3,0.1

Type RM Length L Ch R = 1,5011,478,478,478
BEGIN DESCRIPTION:
Stream0249 11.0
END DESCRIPTION:
XS GIS Cut Line= 3
      1816975.02     13887775.02      1817325.00     13888025.00
      1817725.01     13888025.00
#Sta/Elev= 30
  4569.9 2135.93  4648.5 2127.09  4678.0 2122.38  4713.7 2118.10  4784.9 2111.37
  4835.3 2107.44  4864.8 2106.73  4885.7 2103.86  4906.6 2104.12  4914.0 2105.46
  4950.8 2105.37  4984.3 2101.23  4984.6 2100.73  4988.7 2101.23  5002.5 2101.54
  5030.0 2111.97  5040.0 2114.00  5070.0 2119.43  5090.0 2120.28  5124.8 2126.19
  5130.0 2127.52  5140.0 2127.99  5220.0 2139.06  5250.0 2144.84  5280.0 2153.35
  5290.0 2155.31  5350.0 2173.62  5390.0 2181.93  5397.5 2185.06  5400.0 2185.06
#Mann=4,-1,0
  4569.9    0.07       0  4984.3    0.05       0  4988.7    0.07       0
  5124.8     0.1       0
Bank Sta=4984.3,4988.7
Exp/Cntr=0.3,0.1

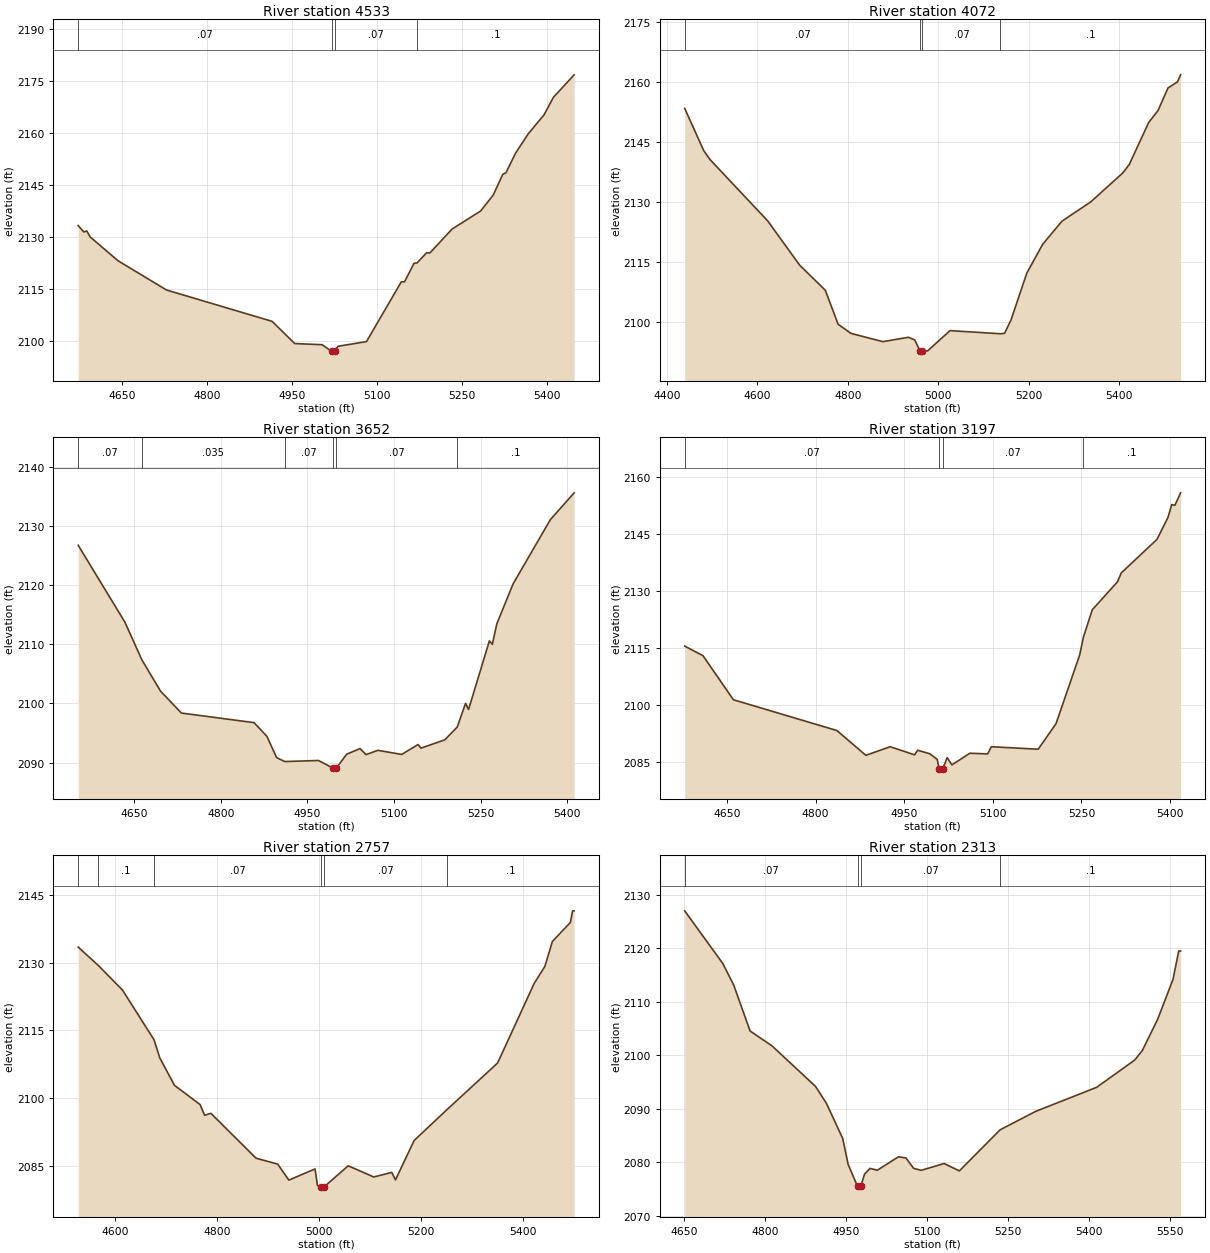
Type RM Length L Ch R = 1,4533,461,461,461
BEGIN DESCRIPTION:
Stream0249 10.0
END DESCRIPTION:
XS GIS Cut Line= 3
      1816925.03     13888624.99      1817325.00     13888475.00
      1817725.01     13888274.99
#Sta/Elev= 30
  4573.2 2133.17  4583.0 2131.33  4588.3 2131.61  4594.5 2129.86  4643.5 2123.01
  4728.9 2114.58  4914.9 2105.55  4955.0 2099.13  5003.2 2098.80  5020.2 2096.87
  5020.6 2096.37  5025.3 2096.87  5031.1 2098.34  5081.4 2099.69  5142.9 2116.95
  5148.5 2116.95  5165.3 2122.29  5170.6 2122.38  5187.6 2125.35  5193.2 2125.26
  5232.4 2132.17  5282.7 2137.37  5305.0 2141.99  5321.8 2147.95  5327.4 2148.41
  5344.2 2154.03  5366.5 2159.61  5394.5 2165.12  5411.2 2170.21  5447.6 2176.66
#Mann=4,-1,0
  4573.2    0.07       0  5020.2    0.05       0  5025.3    0.07       0
  5170.6     0.1       0
Bank Sta=5020.2,5025.3
Exp/Cntr=0.3,0.1

Type RM Length L Ch R = 1,4072,420,420,420
BEGIN DESCRIPTION:
Stream0249 9.0
END DESCRIPTION:
XS GIS Cut Line= 3
      1817075.01     13889274.99      1817475.00     13888875.00
      1817825.01     13888474.98
#Sta/Elev= 30
  4439.1 2153.37  4481.5 2142.74  4495.7 2140.50  4622.9 2125.21  4693.6 2114.14
  4750.2 2107.89  4778.5 2099.40  4806.8 2097.11  4877.5 2095.03  4934.1 2096.12
  4948.2 2095.46  4959.8 2092.66  4960.1 2092.16  4964.9 2092.66  4976.5 2092.71
  5026.1 2097.79  5137.7 2097.00  5146.7 2097.10  5160.9 2100.40  5196.0 2112.15
  5231.1 2119.37  5273.8 2125.16  5337.4 2129.97  5408.6 2137.24  5422.9 2139.38
  5465.6 2149.82  5486.5 2152.85  5508.3 2158.45  5529.2 2159.97  5536.3 2161.75
#Mann=4,-1,0
  4439.1    0.07       0  4959.8    0.05       0  4964.9    0.07       0
  5137.7     0.1       0
Bank Sta=4959.8,4964.9
Exp/Cntr=0.3,0.1

Type RM Length L Ch R = 1,3652,455,455,455
BEGIN DESCRIPTION:
Stream0249 8.0
END DESCRIPTION:
XS GIS Cut Line= 3
      1817274.97     13889425.02      1817675.00     13889225.00
      1818075.04     13889325.01
#Sta/Elev= 30
  4552.7 2126.75  4633.8 2113.72  4662.7 2107.44  4695.3 2102.10  4731.6 2098.38
  4857.4 2096.76  4879.8 2094.45  4896.5 2090.86  4910.6 2090.18  4969.2 2090.36
  4994.4 2089.06  4994.8 2088.56  5000.0 2089.06  5018.0 2091.42  5041.2 2092.37
  5051.5 2091.35  5072.1 2092.08  5113.3 2091.38  5141.7 2093.05  5146.8 2092.45
  5188.1 2093.85  5209.6 2096.01  5224.1 2100.02  5229.3 2098.99  5265.4 2110.59
  5270.5 2110.01  5278.3 2113.47  5306.6 2120.25  5371.0 2131.07  5412.3 2135.62
#Mann=6,-1,0
  4552.7    0.07       0  4662.7   0.035       0  4910.6    0.07       0
  4994.4    0.05       0  5000.0    0.07       0  5209.6     0.1       0
Bank Sta=4994.4,5000
Exp/Cntr=0.3,0.1

Type RM Length L Ch R = 1,3197,440,440,440
BEGIN DESCRIPTION:
Stream0249 7.0
END DESCRIPTION:
XS GIS Cut Line= 3
      1817374.97     13889725.01      1817775.00     13889625.00
      1818174.96     13889475.02
#Sta/Elev= 30
  4578.4 2115.48  4609.4 2112.95  4660.9 2101.32  4836.1 2093.20  4885.1 2086.66
  4926.3 2088.93  4967.6 2086.78  4972.7 2088.00  4993.4 2087.07  5005.9 2085.58
  5009.3 2082.99  5009.7 2082.49  5015.0 2082.99  5022.8 2086.05  5030.8 2084.14
  5061.1 2087.21  5091.3 2087.04  5097.5 2088.93  5176.8 2088.27  5207.0 2095.02
  5247.1 2113.17  5253.2 2117.76  5268.4 2125.07  5311.1 2132.45  5317.4 2134.78
  5377.9 2143.64  5396.6 2149.46  5402.8 2152.82  5408.2 2152.63  5417.9 2155.92
#Mann=4,-1,0
  4578.4    0.07       0  5009.3    0.05       0  5015.0    0.07       0
  5253.2     0.1       0
Bank Sta=5009.3,5015
Exp/Cntr=0.3,0.1

Type RM Length L Ch R = 1,2757,444,444,444
BEGIN DESCRIPTION:
Stream0249 6.0
END DESCRIPTION:
XS GIS Cut Line= 3
      1817375.00     13890225.00      1817775.00     13889975.00
      1818175.00     13889675.00
#Sta/Elev= 30
  4528.4 2133.43  4567.9 2129.35  4615.1 2123.93  4677.0 2112.92  4688.2 2108.92
  4717.1 2102.83  4767.2 2098.59  4776.0 2096.23  4788.4 2096.65  4876.9 2086.72
  4919.3 2085.41  4941.1 2081.87  4992.4 2084.35  4997.2 2080.70  5004.5 2080.38
  5005.0 2079.88  5010.2 2080.38  5057.4 2085.04  5107.4 2082.57  5142.8 2083.58
  5150.1 2081.93  5186.6 2090.64  5251.7 2097.55  5350.1 2107.78  5422.0 2125.43
  5442.8 2129.17  5457.4 2134.66  5492.8 2138.90  5497.0 2141.45  5500.1 2141.45
#Mann=6,-1,0
  4528.4    0.07       0  4567.9     0.1       0  4677.0    0.07       0
  5004.5    0.05       0  5010.2    0.07       0  5251.7     0.1       0
Bank Sta=5004.5,5010.2
Exp/Cntr=0.3,0.1

Type RM Length L Ch R = 1,2313,422,422,422
BEGIN DESCRIPTION:
Stream0249 5.0
END DESCRIPTION:
XS GIS Cut Line= 3
      1817475.00     13890425.00      1817825.00     13890375.00
      1818224.97     13889975.03
#Sta/Elev= 30
  4651.2 2126.97  4721.9 2117.13  4742.1 2113.10  4772.4 2104.53  4812.8 2101.77
  4893.6 2094.19  4913.8 2091.04  4944.1 2084.46  4954.2 2079.60  4971.6 2075.49
  4972.0 2074.99  4977.4 2075.49  4984.6 2077.79  4994.7 2078.86  5008.3 2078.52
  5047.2 2081.02  5061.3 2080.82  5075.5 2078.88  5089.6 2078.50  5132.0 2079.77
  5160.3 2078.40  5235.9 2086.07  5301.7 2089.51  5414.9 2094.01  5485.6 2099.12
  5499.7 2100.93  5528.0 2106.75  5556.3 2114.17  5566.9 2119.47  5570.4 2119.47
#Mann=4,-1,0
  4651.2    0.07       0  4971.6    0.05       0  4977.4    0.07       0
  5235.9     0.1       0
Bank Sta=4971.6,4977.4
Exp/Cntr=0.3,0.1

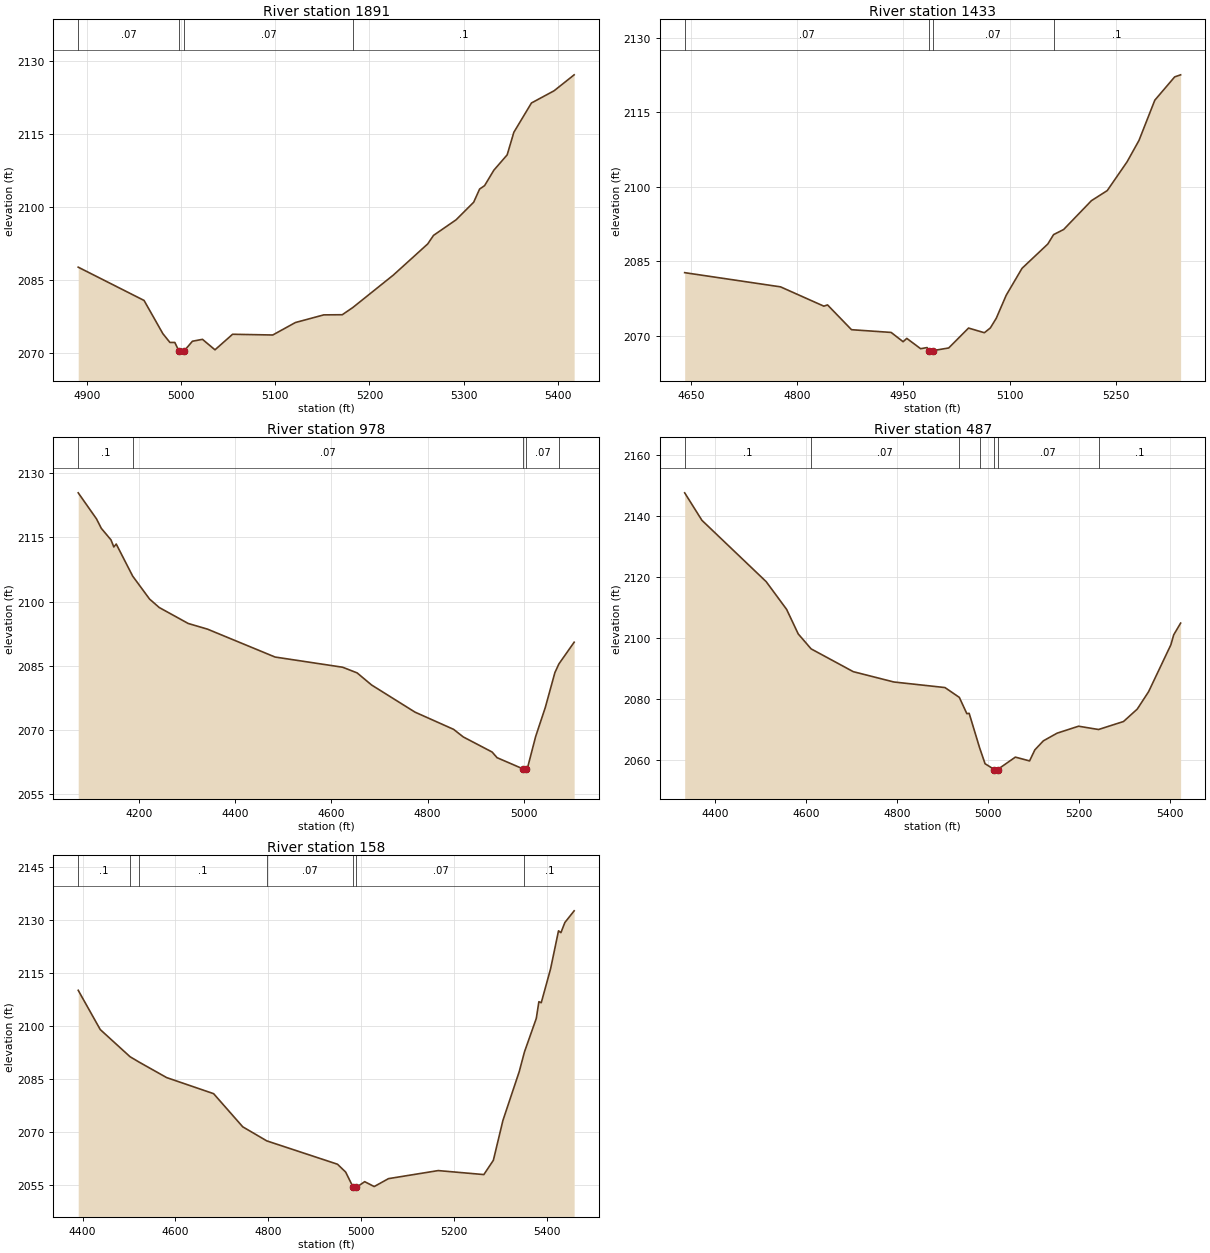
Type RM Length L Ch R = 1,1891,458,458,458
BEGIN DESCRIPTION:
Stream0249 4.0
END DESCRIPTION:
XS GIS Cut Line= 3
      1817924.97     13890725.00      1818025.00     13890725.00
      1818424.97     13890575.01
#Sta/Elev= 30
  4890.4 2087.60  4960.4 2080.77  4980.4 2073.95  4987.9 2072.15  4993.1 2072.15
  4997.3 2070.46  4997.8 2069.96  5003.2 2070.46  5011.8 2072.40  5022.5 2072.79
  5035.8 2070.64  5054.5 2073.83  5097.2 2073.68  5121.3 2076.24  5151.5 2077.81
  5171.1 2077.84  5182.4 2079.33  5225.4 2085.98  5261.9 2092.36  5268.1 2094.12
  5292.1 2097.32  5310.8 2100.93  5317.1 2103.63  5322.4 2104.33  5332.2 2107.49
  5346.4 2110.65  5353.5 2115.28  5372.2 2121.29  5396.3 2123.80  5417.6 2127.07
#Mann=4,-1,0
  4890.4    0.07       0  4997.3    0.05       0  5003.2    0.07       0
  5182.4     0.1       0
Bank Sta=4997.3,5003.2
Exp/Cntr=0.3,0.1

Type RM Length L Ch R = 1,1433,455,455,455
BEGIN DESCRIPTION:
Stream0249 3.0
END DESCRIPTION:
XS GIS Cut Line= 3
      1817974.97     13890924.99      1818325.00     13891025.00
      1818475.02     13890724.96
#Sta/Elev= 30
  4641.5 2082.70  4776.7 2079.84  4837.8 2075.95  4843.0 2076.20  4876.8 2071.21
  4932.7 2070.66  4949.6 2068.79  4954.8 2069.46  4974.3 2067.38  4983.4 2067.61
  4985.7 2066.99  4986.2 2066.49  4991.6 2066.99  5013.9 2067.53  5041.9 2071.54
  5064.2 2070.60  5072.6 2071.56  5081.0 2073.52  5095.0 2078.15  5117.3 2083.57
  5153.7 2088.47  5161.8 2090.36  5176.0 2091.39  5215.2 2097.20  5237.5 2099.23
  5265.5 2105.03  5282.3 2109.34  5304.6 2117.44  5332.6 2122.13  5341.0 2122.55
#Mann=4,-1,0
  4641.5    0.07       0  4985.7    0.05       0  4991.6    0.07       0
  5161.8     0.1       0
Bank Sta=4985.7,4991.6
Exp/Cntr=0.3,0.1

Type RM Length L Ch R = 1,978,491,491,491
BEGIN DESCRIPTION:
Stream0249 2.0
END DESCRIPTION:
XS GIS Cut Line= 3
      1817247.11     13891354.31      1818175.00     13891425.00
      1818275.02     13891425.00
#Sta/Elev= 30
  4074.0 2125.38  4112.0 2119.30  4122.0 2117.09  4142.1 2114.40  4148.0 2112.75
  4153.0 2113.43  4187.2 2105.94  4222.3 2100.58  4242.4 2098.61  4302.5 2094.89
  4342.7 2093.56  4483.1 2087.05  4623.5 2084.67  4653.6 2083.35  4683.6 2080.53
  4773.9 2074.19  4854.1 2070.17  4874.2 2068.40  4934.1 2064.88  4944.4 2063.56
  4998.8 2060.92  4999.3 2060.42  5004.9 2060.42  5005.4 2060.92  5007.1 2060.92
  5024.6 2068.50  5044.6 2075.26  5064.6 2083.42  5072.9 2085.44  5104.6 2090.51
#Mann=5,-1,0
  4074.0     0.1       0  4187.2    0.07       0  4998.8    0.05       0
  5005.4    0.07       0  5072.9     0.1       0
Bank Sta=4998.8,5005.4
Exp/Cntr=0.3,0.1

Type RM Length L Ch R = 1,487,329,329,329
BEGIN DESCRIPTION:
Stream0249 1.0
END DESCRIPTION:
XS GIS Cut Line= 3
      1817167.36     13891691.96      1817825.00     13891775.00
      1818225.03     13891925.01
#Sta/Elev= 30
  4333.3 2147.50  4371.2 2138.50  4512.4 2118.42  4557.4 2109.32  4582.9 2101.29
  4611.2 2096.40  4703.9 2088.93  4793.1 2085.55  4905.4 2083.73  4937.0 2080.51
  4953.5 2075.18  4958.6 2075.29  4981.6 2063.99  4993.6 2058.78  5014.2 2056.86
  5014.7 2056.36  5020.9 2056.86  5060.2 2060.95  5091.4 2059.70  5103.0 2063.32
  5121.7 2066.28  5151.9 2068.79  5199.1 2071.07  5243.0 2069.99  5297.9 2072.61
  5328.1 2076.68  5353.1 2082.40  5402.0 2097.74  5408.2 2100.99  5423.4 2104.83
#Mann=7,-1,0
  4333.3     0.1       0  4611.2    0.07       0  4937.0     0.1       0
  4981.6    0.07       0  5014.2    0.05       0  5020.9    0.07       0
  5243.0     0.1       0
Bank Sta=5014.2,5020.9
Exp/Cntr=0.3,0.1

Type RM Length L Ch R = 1,158,0,0,0
BEGIN DESCRIPTION:
Stream0249 0.0
END DESCRIPTION:
XS GIS Cut Line= 3
      1817324.22     13891870.59      1817699.93     13892132.61
      1818294.43     13891992.68
#Sta/Elev= 30
  4390.6 2110.10  4438.1 2098.98  4502.4 2091.28  4522.6 2089.71  4581.2 2085.38
  4682.4 2080.83  4745.2 2071.44  4797.0 2067.46  4949.4 2060.85  4966.9 2058.64
  4983.3 2054.30  4983.8 2053.80  4990.0 2054.30  5008.0 2055.91  5028.5 2054.53
  5059.3 2056.77  5166.4 2059.05  5264.8 2057.92  5285.3 2061.97  5305.9 2073.25
  5341.0 2087.05  5352.3 2092.64  5377.8 2102.14  5383.4 2106.87  5388.5 2106.58
  5408.6 2116.18  5425.7 2126.94  5430.9 2126.42  5439.4 2129.29  5459.4 2132.60
#Mann=7,-1,0
  4390.6     0.1       0  4502.4    0.07       0  4522.6     0.1       0
  4797.0    0.07       0  4983.3    0.05       0  4990.0    0.07       0
  5352.3     0.1       0
Bank Sta=4983.3,4990
Exp/Cntr=0.3,0.1

Chan Stop Cuts=-1