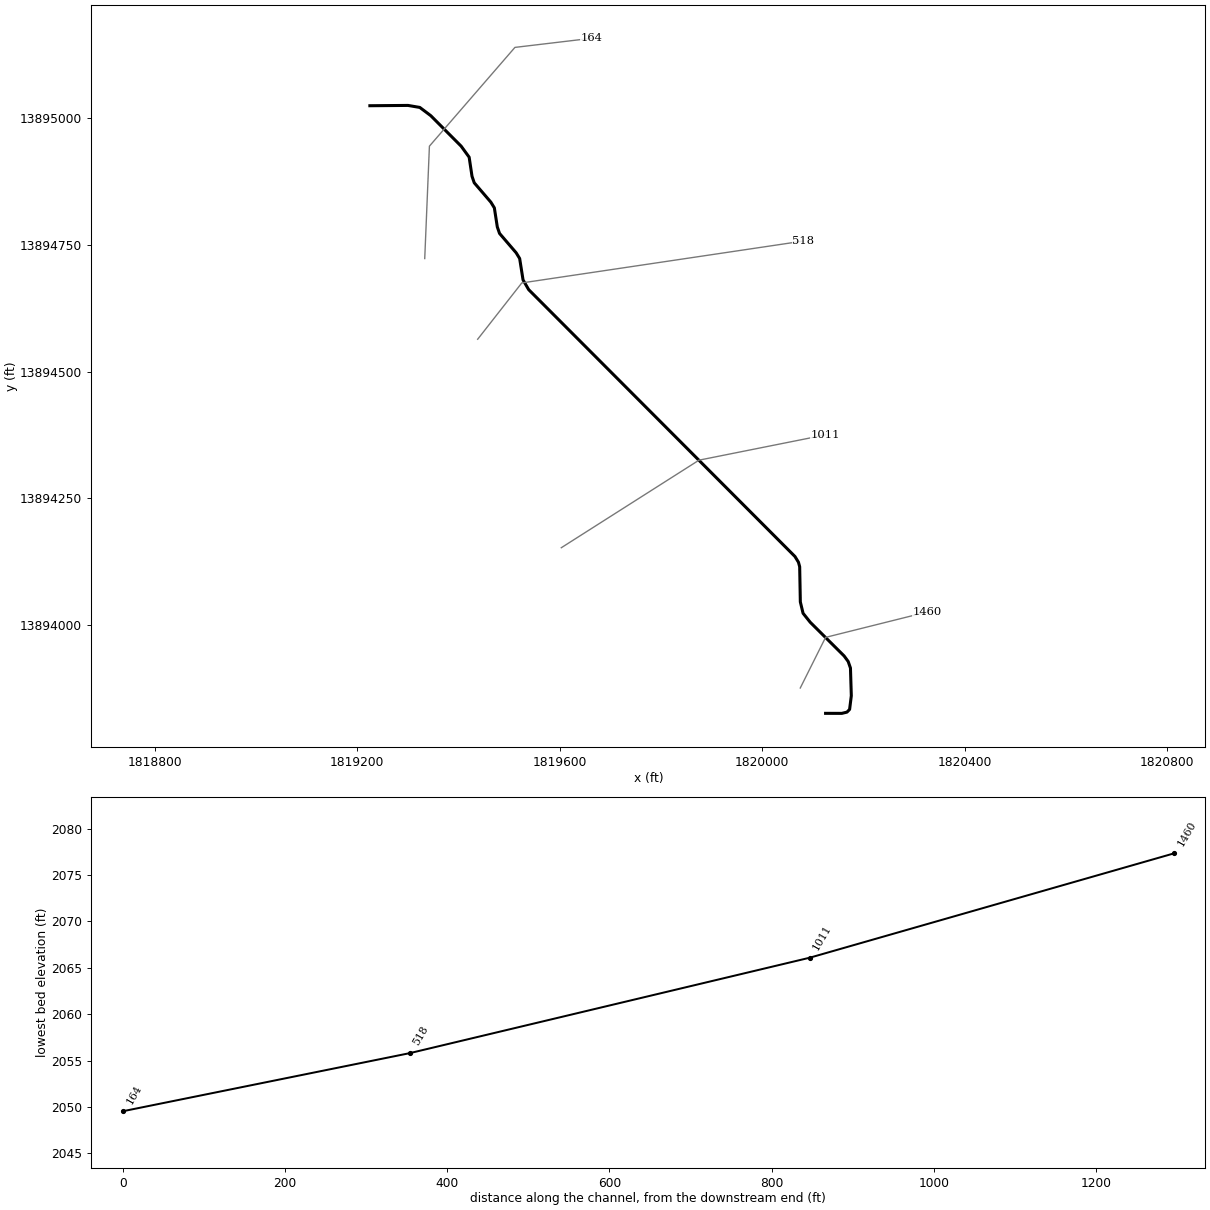
--- Stream0250.prj (project) ---

Proj Title=Stream0250 Base Level Engineering
Current Plan=p01
Default Exp/Contr=0.3,0.1
English Units
Geom File=g01
Flow File=f01
Plan File=p01
BEGIN DESCRIPTION:
Stream0250
END DESCRIPTION:

--- Stream0250.p01 (plan) ---

Plan Title=Multiple Run
Short Identifier=Multiple
Geom File=g01
Flow File=f01
Subcritical Flow
K Sum by GR= 0
Std Step Tol= 0.01
Critical Tol= 0.01
Num of Std Step Trials= 20
Max Error Tol= 0.3
Flow Tol Ratio= 0.001
Split Flow NTrial= 30
Split Flow Tol= 0.02
Split Flow Ratio= 0.02
Log Output Level= 0
Friction Slope Method= 1
Unsteady Friction Slope Method= 2
Unsteady Bridges Friction Slope Method= 1
Parabolic Critical Depth
Global Vel Dist=  1 , 1 , 1
Global Log Level= 0
CheckData=True
Encroach Param= -1, 0, 0, 0
BEGIN DESCRIPTION:
Multiple Run
END DESCRIPTION:

--- Stream0250.f01 (steady flow) ---

Flow Title=Multiple
Number of Profiles=7
Profile Names=10-year,25-year,50-year,1pct_min,100-year,1pct_plu,500-year
River Rch & RM= Stream0250,Reach-1,1460
     573     954    1307     869    1735    3461    3015
Boundary for River Rch & Prof#=Stream0250,Reach-1,1
Up Type=0
Dn Type=3
Dn Slope=0.005
Boundary for River Rch & Prof#=Stream0250,Reach-1,2
Up Type=0
Dn Type=3
Dn Slope=0.005
Boundary for River Rch & Prof#=Stream0250,Reach-1,3
Up Type=0
Dn Type=3
Dn Slope=0.005
Boundary for River Rch & Prof#=Stream0250,Reach-1,4
Up Type=0
Dn Type=3
Dn Slope=0.005
Boundary for River Rch & Prof#=Stream0250,Reach-1,5
Up Type=0
Dn Type=3
Dn Slope=0.005
Boundary for River Rch & Prof#=Stream0250,Reach-1,6
Up Type=0
Dn Type=3
Dn Slope=0.005
Boundary for River Rch & Prof#=Stream0250,Reach-1,7
Up Type=0
Dn Type=3
Dn Slope=0.005

--- Stream0250.g01 (geometry) ---

Geom Title=Existing Conditions

River Reach=Stream0250,Reach-1
Reach XY= 30
      1820125.00     13893825.00      1820157.01     13893824.92
      1820167.28     13893827.41      1820172.44     13893832.76
      1820175.81     13893859.72      1820174.12     13893914.47
      1820169.62     13893927.40      1820161.64     13893938.28
      1820094.67     13894004.86      1820080.54     13894022.58
      1820075.14     13894045.06      1820073.83     13894114.52
      1820071.39     13894123.50      1820064.48     13894134.79
      1819538.62     13894661.79      1819527.50     13894681.03
      1819520.81     13894723.26      1819513.90     13894734.54
      1819481.08     13894772.80      1819476.65     13894785.69
      1819470.84     13894823.28      1819463.92     13894834.55
      1819431.10     13894872.82      1819426.70     13894885.71
      1819421.06     13894923.38      1819405.24     13894945.13
      1819345.20     13895005.40      1819323.61     13895021.62
      1819300.25     13895025.60      1819225.00     13895025.00

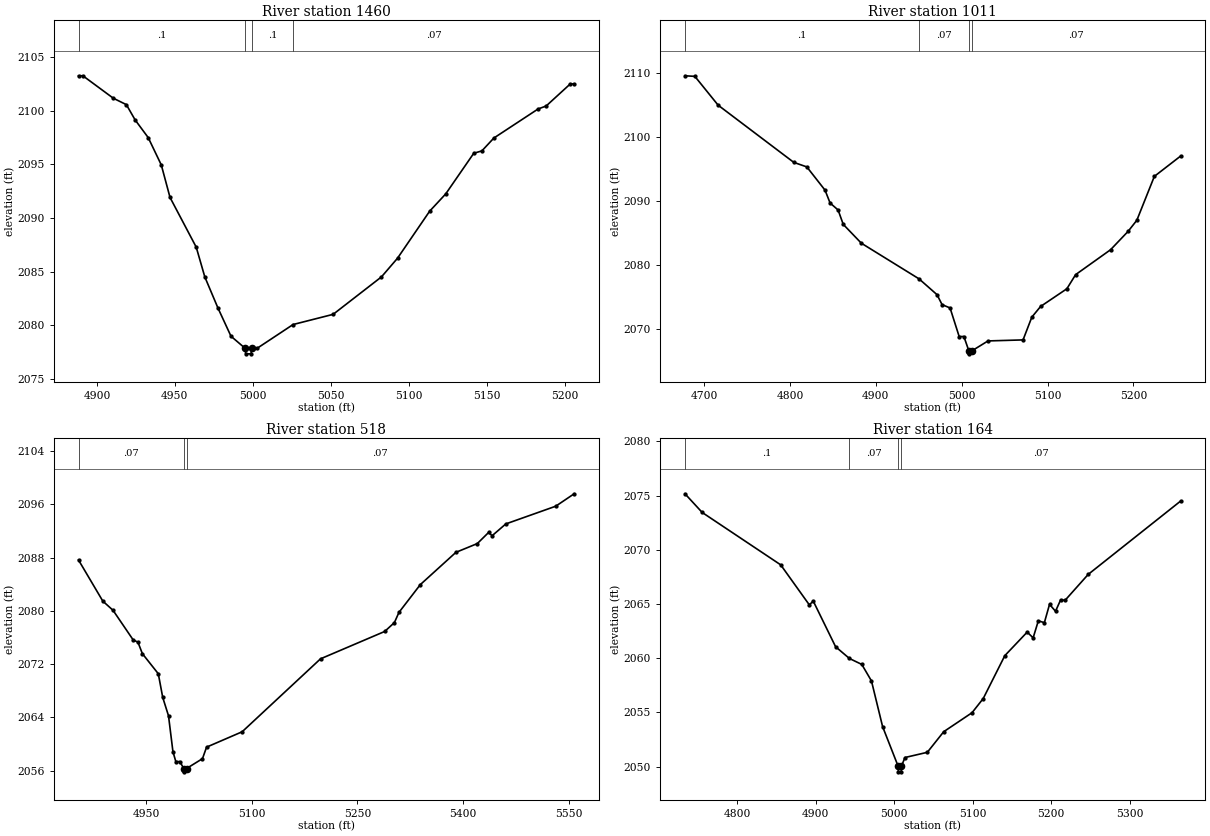
Type RM Length L Ch R = 1,1460,449,449,449
BEGIN DESCRIPTION:
Stream0250 3.0
END DESCRIPTION:
XS GIS Cut Line= 3
      1820075.01     13893875.01      1820125.00     13893975.00
      1820324.96     13894024.99
#Sta/Elev= 30
  4888.2 2103.25  4891.0 2103.25  4910.5 2101.16  4918.9 2100.56  4924.5 2099.14
  4932.9 2097.49  4941.3 2094.94  4946.9 2091.91  4963.7 2087.28  4969.2 2084.51
  4977.6 2081.62  4986.0 2078.98  4995.2 2077.84  4995.4 2077.34  4998.9 2077.34
  4999.2 2077.84  5002.6 2077.84  5025.8 2080.07  5051.5 2081.02  5082.5 2084.51
  5092.8 2086.25  5113.4 2090.63  5123.7 2092.24  5141.7 2096.03  5146.9 2096.25
  5154.6 2097.45  5183.0 2100.16  5188.1 2100.43  5203.6 2102.49  5206.1 2102.49
#Mann=4,-1,0
  4888.2     0.1       0  4995.2    0.05       0  4999.2     0.1       0
  5025.8    0.07       0
Bank Sta=4995.2,4999.2
Exp/Cntr=0.3,0.1

Type RM Length L Ch R = 1,1011,493,493,493
BEGIN DESCRIPTION:
Stream0250 2.0
END DESCRIPTION:
XS GIS Cut Line= 3
      1819603.04     13894152.07      1819875.00     13894325.00
      1820124.97     13894374.99
#Sta/Elev= 30
  4677.7 2109.60  4689.2 2109.51  4716.3 2105.00  4804.4 2096.05  4819.6 2095.34
  4840.8 2091.70  4846.7 2089.69  4856.0 2088.60  4862.0 2086.35  4883.1 2083.40
  4950.3 2077.82  4971.2 2075.35  4977.1 2073.79  4986.4 2073.27  4997.0 2068.80
  5002.5 2068.80  5008.2 2066.59  5008.4 2066.09  5012.2 2066.59  5030.6 2068.11
  5071.4 2068.27  5081.6 2071.83  5091.8 2073.50  5122.4 2076.27  5132.6 2078.48
  5173.3 2082.38  5193.7 2085.25  5203.9 2086.99  5224.3 2093.86  5254.9 2097.04
#Mann=4,-1,0
  4677.7     0.1       0  4950.3    0.07       0  5008.2    0.05       0
  5012.2    0.07       0
Bank Sta=5008.2,5012.2
Exp/Cntr=0.3,0.1

Type RM Length L Ch R = 1,518,354,354,354
BEGIN DESCRIPTION:
Stream0250 1.0
END DESCRIPTION:
XS GIS Cut Line= 3
      1819437.90     13894563.82      1819525.00     13894675.00
      1820080.94     13894757.75
#Sta/Elev= 30
  4854.3 2087.63  4888.8 2081.45  4903.3 2080.07  4932.0 2075.60  4938.6 2075.29
  4944.9 2073.56  4967.5 2070.54  4973.8 2066.98  4982.0 2064.22  4988.3 2058.82
  4992.4 2057.34  4998.1 2057.34  5003.6 2056.30  5003.9 2055.80  5007.6 2056.30
  5030.2 2057.78  5036.0 2059.51  5086.5 2061.82  5197.7 2072.78  5288.7 2076.89
  5302.5 2078.22  5309.0 2079.76  5339.3 2083.93  5389.8 2088.78  5420.2 2090.10
  5436.2 2091.77  5441.2 2091.28  5460.6 2093.05  5531.4 2095.71  5557.6 2097.58
#Mann=3,-1,0
  4854.3    0.07       0  5003.6    0.05       0  5007.6    0.07       0
Bank Sta=5003.6,5007.6
Exp/Cntr=0.3,0.1

Type RM Length L Ch R = 1,164,0,0,0
BEGIN DESCRIPTION:
Stream0250 0.0
END DESCRIPTION:
XS GIS Cut Line= 4
      1819333.34     13894723.15      1819342.58     13894945.13
      1819511.47     13895140.19      1819662.02     13895158.09
#Sta/Elev= 30
  4733.2 2075.16  4755.1 2073.44  4855.2 2068.61  4891.7 2064.92  4896.7 2065.27
  4925.2 2061.06  4942.8 2059.98  4958.6 2059.43  4970.9 2057.91  4985.1 2053.70
  5005.0 2050.03  5005.3 2049.53  5008.8 2049.53  5009.0 2050.03  5013.6 2050.85
  5042.1 2051.33  5063.0 2053.23  5099.1 2054.98  5113.4 2056.29  5140.9 2060.24
  5169.4 2062.41  5177.0 2061.88  5183.6 2063.45  5191.3 2063.28  5197.9 2064.97
  5205.5 2064.33  5212.1 2065.39  5217.7 2065.34  5247.2 2067.73  5365.0 2074.49
#Mann=4,-1,0
  4733.2     0.1       0  4942.8    0.07       0  5005.0    0.05       0
  5009.0    0.07       0
Bank Sta=5005,5009
Exp/Cntr=0.3,0.1

Chan Stop Cuts=-1