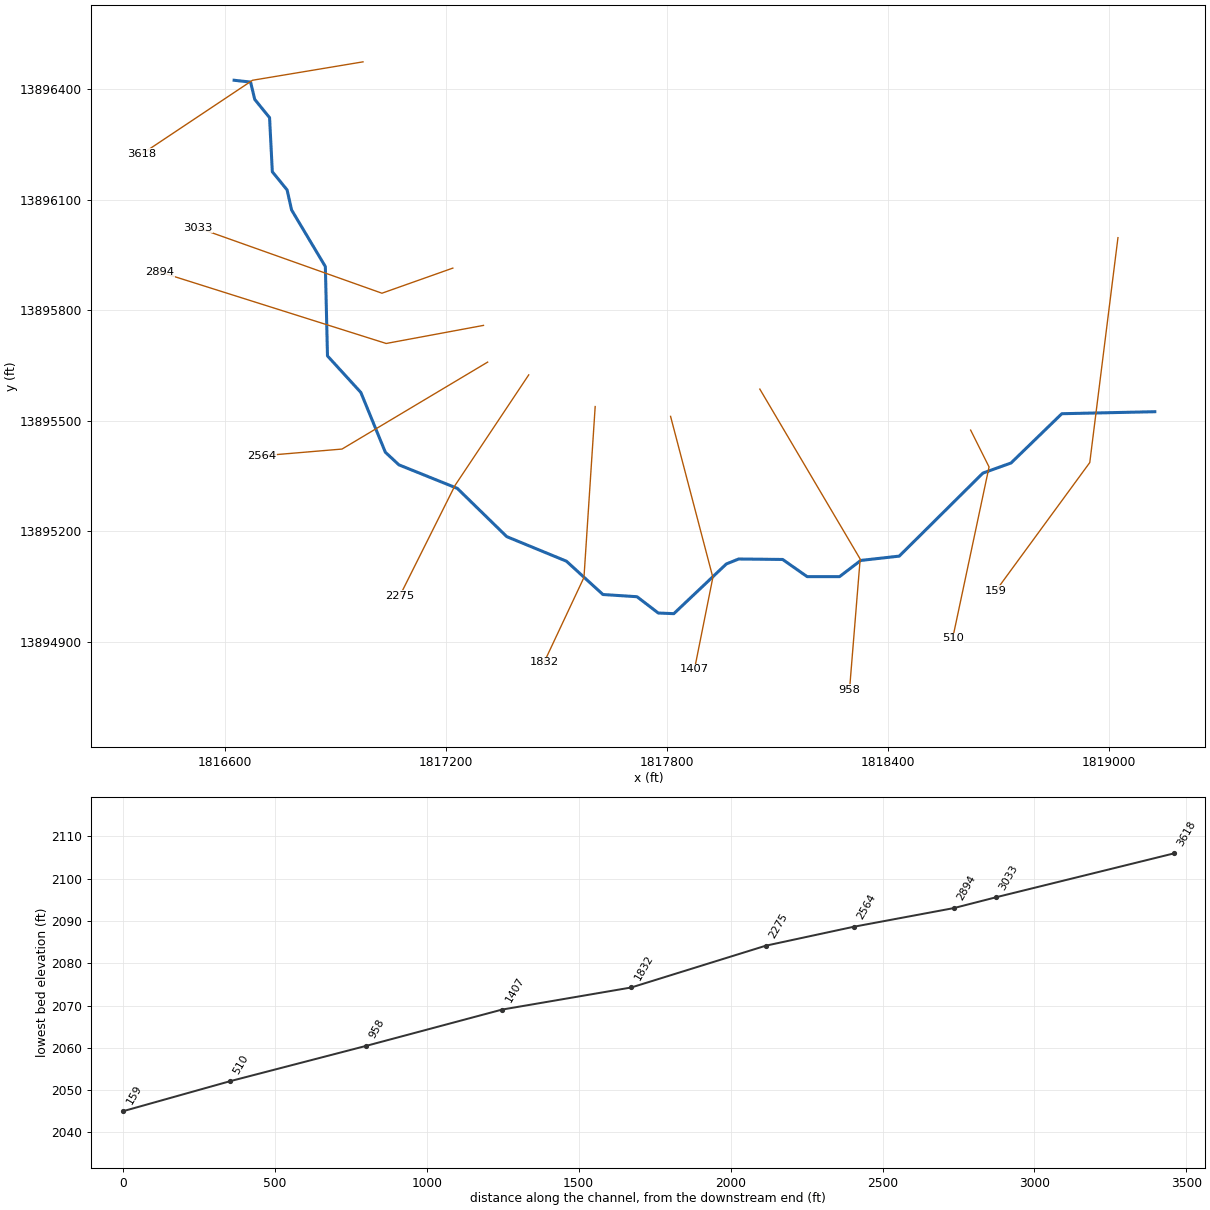
--- Stream0251.prj (project) ---

Proj Title=Stream0251 Base Level Engineering
Current Plan=p01
Default Exp/Contr=0.3,0.1
English Units
Geom File=g01
Flow File=f01
Plan File=p01
BEGIN DESCRIPTION:
Stream0251
END DESCRIPTION:

--- Stream0251.p01 (plan) ---

Plan Title=Multiple Run
Short Identifier=Multiple
Geom File=g01
Flow File=f01
Subcritical Flow
K Sum by GR= 0
Std Step Tol= 0.01
Critical Tol= 0.01
Num of Std Step Trials= 20
Max Error Tol= 0.3
Flow Tol Ratio= 0.001
Split Flow NTrial= 30
Split Flow Tol= 0.02
Split Flow Ratio= 0.02
Log Output Level= 0
Friction Slope Method= 1
Unsteady Friction Slope Method= 2
Unsteady Bridges Friction Slope Method= 1
Parabolic Critical Depth
Global Vel Dist=  1 , 1 , 1
Global Log Level= 0
CheckData=True
Encroach Param= -1, 0, 0, 0
BEGIN DESCRIPTION:
Multiple Run
END DESCRIPTION:

--- Stream0251.f01 (steady flow) ---

Flow Title=Multiple
Number of Profiles=7
Profile Names=10-year,25-year,50-year,1pct_min,100-year,1pct_plu,500-year
River Rch & RM= Stream0251,Reach-1,3618
     508     833    1131     744    1485    2963    2529
Boundary for River Rch & Prof#=Stream0251,Reach-1,1
Up Type=0
Dn Type=3
Dn Slope=0.005
Boundary for River Rch & Prof#=Stream0251,Reach-1,2
Up Type=0
Dn Type=3
Dn Slope=0.005
Boundary for River Rch & Prof#=Stream0251,Reach-1,3
Up Type=0
Dn Type=3
Dn Slope=0.005
Boundary for River Rch & Prof#=Stream0251,Reach-1,4
Up Type=0
Dn Type=3
Dn Slope=0.005
Boundary for River Rch & Prof#=Stream0251,Reach-1,5
Up Type=0
Dn Type=3
Dn Slope=0.005
Boundary for River Rch & Prof#=Stream0251,Reach-1,6
Up Type=0
Dn Type=3
Dn Slope=0.005
Boundary for River Rch & Prof#=Stream0251,Reach-1,7
Up Type=0
Dn Type=3
Dn Slope=0.005

--- Stream0251.g01 (geometry) ---

Geom Title=Existing Conditions

River Reach=Stream0251,Reach-1
Reach XY= 30
      1816625.00     13896425.00      1816669.72     13896420.10
      1816681.04     13896373.00      1816721.27     13896323.47
      1816728.76     13896176.56      1816768.88     13896127.18
      1816781.08     13896072.80      1816872.76     13895919.07
      1816878.55     13895676.47      1816969.15     13895577.29
      1817035.63     13895415.00      1817072.45     13895380.73
      1817231.06     13895316.86      1817365.32     13895185.77
      1817527.29     13895119.15      1817626.50     13895028.62
      1817719.03     13895022.62      1817776.75     13894978.34
      1817818.97     13894976.62      1817961.68     13895111.63
      1817994.99     13895125.06      1818114.49     13895123.79
      1818180.98     13895077.17      1818269.03     13895077.17
      1818326.60     13895121.14      1818431.17     13895132.86
      1818658.33     13895358.35      1818734.68     13895385.78
      1818872.55     13895519.54      1819125.00     13895525.00

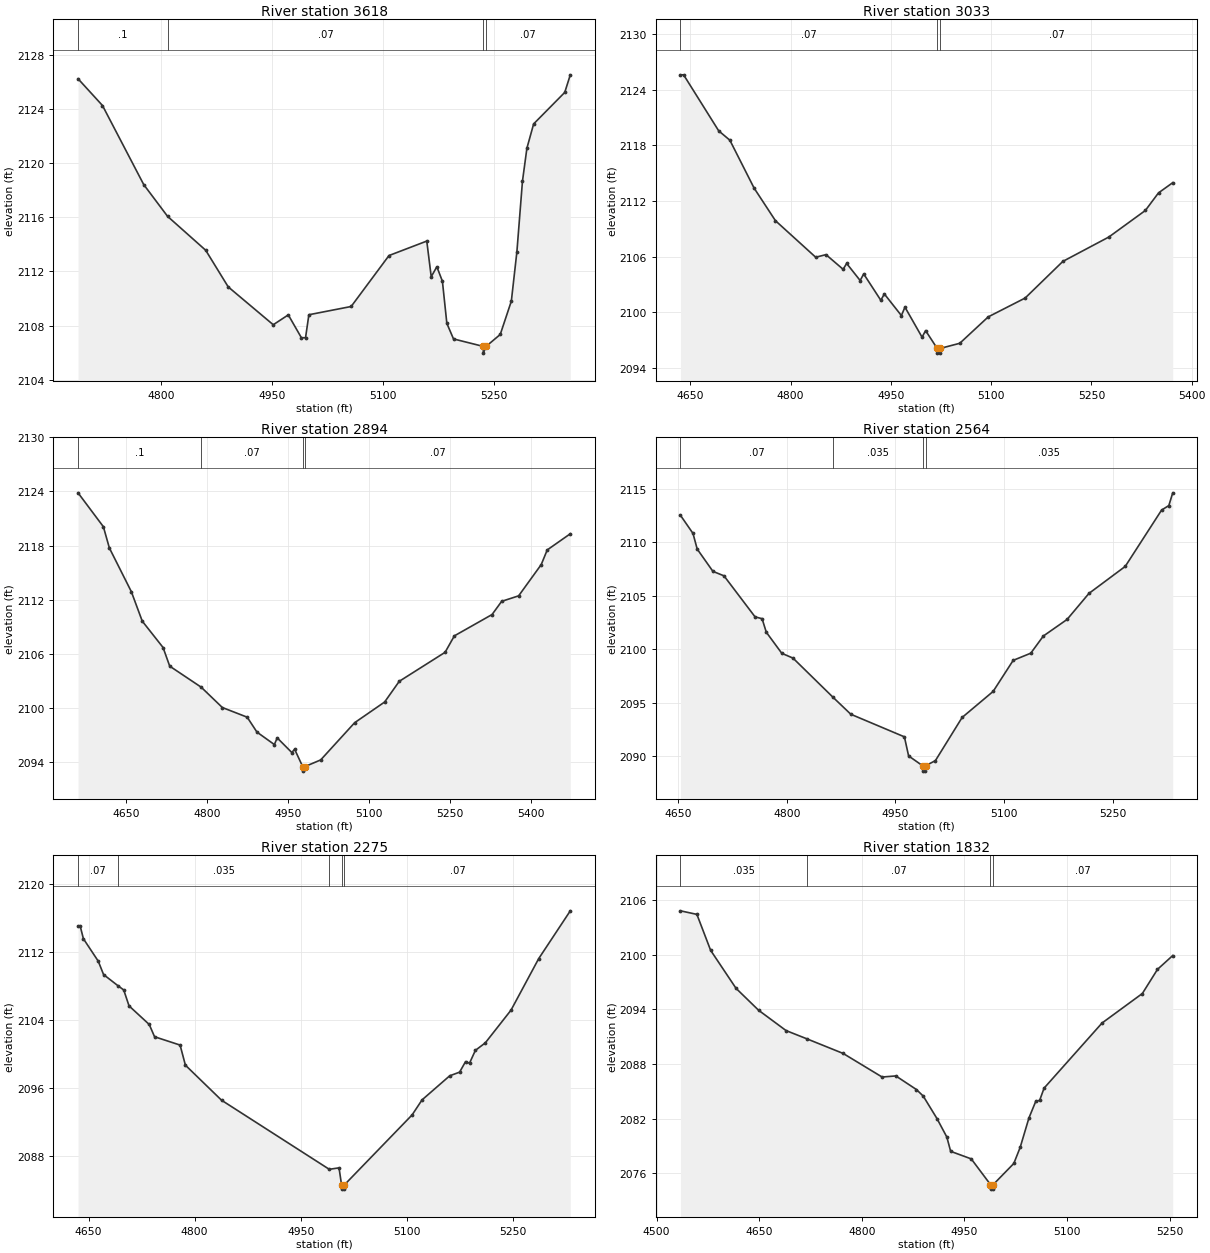
Type RM Length L Ch R = 1,3618,585,585,585
BEGIN DESCRIPTION:
Stream0251 8.0
END DESCRIPTION:
XS GIS Cut Line= 3
      1816975.03     13896475.01      1816675.00     13896425.00
      1816375.02     13896225.02
#Sta/Elev= 30
  4688.3 2126.26  4721.3 2124.28  4777.0 2118.43  4809.2 2116.08  4860.7 2113.57
  4891.1 2110.86  4951.9 2108.06  4972.2 2108.79  4989.9 2107.10  4995.5 2107.10
  5000.0 2108.80  5057.1 2109.41  5108.2 2113.18  5159.2 2114.25  5165.2 2111.61
  5172.8 2112.35  5180.3 2111.28  5186.3 2108.16  5195.3 2107.01  5235.3 2106.46
  5235.6 2105.96  5239.3 2106.46  5258.4 2107.34  5273.4 2109.81  5280.9 2113.47
  5288.4 2118.68  5294.4 2121.12  5303.5 2122.92  5345.5 2125.25  5353.0 2126.55
#Mann=4,-1,0
  4688.3     0.1       0  4809.2    0.07       0  5235.3    0.05       0
  5239.3    0.07       0
Bank Sta=5235.3,5239.3
Exp/Cntr=0.3,0.1

Type RM Length L Ch R = 1,3033,139,139,139
BEGIN DESCRIPTION:
Stream0251 7.0
END DESCRIPTION:
XS GIS Cut Line= 3
      1817218.90     13895914.94      1817026.41     13895846.76
      1816524.96     13896025.02
#Sta/Elev= 30
  4635.3 2125.61  4640.0 2125.61  4692.5 2119.57  4709.2 2118.56  4745.5 2113.39
  4777.4 2109.88  4837.6 2105.94  4853.0 2106.22  4878.6 2104.64  4883.9 2105.27
  4904.1 2103.43  4909.4 2104.14  4935.0 2101.30  4940.3 2101.98  4965.8 2099.65
  4971.1 2100.56  4996.7 2097.32  5002.0 2098.03  5019.4 2096.10  5019.7 2095.60
  5023.2 2095.60  5023.4 2096.10  5053.1 2096.66  5095.7 2099.51  5150.9 2101.54
  5207.3 2105.49  5276.1 2108.12  5330.7 2110.98  5350.4 2112.88  5371.7 2113.98
#Mann=3,-1,0
  4635.3    0.07       0  5019.4    0.05       0  5023.4    0.07       0
Bank Sta=5019.4,5023.4
Exp/Cntr=0.3,0.1

Type RM Length L Ch R = 1,2894,330,330,330
BEGIN DESCRIPTION:
Stream0251 6.0
END DESCRIPTION:
XS GIS Cut Line= 3
      1817302.10     13895759.35      1817037.96     13895710.29
      1816423.63     13895904.30
#Sta/Elev= 30
  4560.3 2123.84  4607.3 2120.09  4618.4 2117.74  4659.1 2112.91  4679.4 2109.64
  4718.0 2106.72  4730.3 2104.66  4788.7 2102.33  4827.9 2100.08  4874.0 2099.01
  4892.1 2097.36  4924.4 2095.98  4929.7 2096.72  4956.7 2095.10  4962.0 2095.46
  4976.9 2093.54  4977.1 2093.04  4980.9 2093.54  5010.3 2094.28  5073.3 2098.40
  5128.9 2100.69  5156.0 2102.98  5241.0 2106.19  5258.2 2108.01  5328.1 2110.37
  5345.9 2111.83  5377.4 2112.44  5419.3 2115.90  5430.4 2117.52  5473.2 2119.31
#Mann=4,-1,0
  4560.3     0.1       0  4788.7    0.07       0  4976.9    0.05       0
  4980.9    0.07       0
Bank Sta=4976.9,4980.9
Exp/Cntr=0.3,0.1

Type RM Length L Ch R = 1,2564,289,289,289
BEGIN DESCRIPTION:
Stream0251 5.1
END DESCRIPTION:
XS GIS Cut Line= 3
      1817313.45     13895659.71      1816918.10     13895423.60
      1816699.67     13895405.15
#Sta/Elev= 30
  4653.3 2112.50  4670.6 2110.81  4676.4 2109.35  4698.1 2107.27  4713.4 2106.85
  4756.3 2103.02  4766.0 2102.85  4771.8 2101.59  4793.2 2099.62  4808.7 2099.17
  4863.7 2095.53  4888.5 2093.93  4962.5 2091.82  4968.3 2090.04  4987.7 2089.12
  4987.9 2088.62  4991.4 2088.62  4991.7 2089.12  5005.3 2089.60  5042.2 2093.63
  5085.0 2096.06  5112.7 2098.96  5137.0 2099.63  5154.3 2101.23  5187.1 2102.78
  5217.3 2105.21  5267.4 2107.73  5317.6 2112.99  5327.6 2113.41  5333.0 2114.60
#Mann=4,-1,0
  4653.3    0.07       0  4863.7   0.035       0  4987.7   0.035       0
  4991.7   0.035       0
Bank Sta=4987.7,4991.7
Exp/Cntr=0.3,0.1

Type RM Length L Ch R = 1,2275,443,443,443
BEGIN DESCRIPTION:
Stream0251 5.0
END DESCRIPTION:
XS GIS Cut Line= 3
      1817425.02     13895625.03      1817225.00     13895325.00
      1817075.00     13895025.00
#Sta/Elev= 30
  4635.1 2115.08  4638.1 2115.08  4642.7 2113.58  4663.7 2110.94  4671.2 2109.37
  4691.2 2108.08  4699.7 2107.56  4707.2 2105.69  4735.8 2103.50  4743.3 2102.06
  4779.4 2101.08  4786.9 2098.72  4838.0 2094.60  4990.3 2086.48  5004.1 2086.65
  5007.7 2084.65  5007.9 2084.15  5011.4 2084.15  5011.7 2084.65  5107.5 2092.88
  5121.5 2094.64  5160.6 2097.47  5174.6 2097.90  5183.0 2099.14  5188.6 2098.95
  5196.9 2100.46  5210.9 2101.34  5247.3 2105.19  5286.4 2111.24  5331.1 2116.86
#Mann=5,-1,0
  4635.1    0.07       0  4691.2   0.035       0  4990.3    0.07       0
  5007.7    0.05       0  5011.7    0.07       0
Bank Sta=5007.7,5011.7
Exp/Cntr=0.3,0.1

Type RM Length L Ch R = 1,1832,425,425,425
BEGIN DESCRIPTION:
Stream0251 4.0
END DESCRIPTION:
XS GIS Cut Line= 3
      1817605.45     13895538.98      1817575.00     13895075.00
      1817466.91     13894844.79
#Sta/Elev= 30
  4535.0 2104.83  4559.0 2104.44  4579.1 2100.49  4616.2 2096.32  4649.2 2093.91
  4689.3 2091.68  4719.2 2090.79  4772.7 2089.17  4829.6 2086.58  4849.7 2086.70
  4879.7 2085.21  4889.7 2084.49  4909.8 2082.02  4924.2 2079.99  4929.8 2078.42
  4959.9 2077.59  4988.0 2074.77  4988.2 2074.27  4991.7 2074.27  4992.0 2074.77
  5022.1 2077.09  5031.4 2078.86  5044.2 2082.09  5054.2 2083.92  5059.8 2084.01
  5066.3 2085.36  5151.0 2092.51  5209.9 2095.75  5232.0 2098.40  5254.3 2099.92
#Mann=4,-1,0
  4535.0   0.035       0  4719.2    0.07       0  4988.0    0.05       0
  4992.0    0.07       0
Bank Sta=4988,4992
Exp/Cntr=0.3,0.1

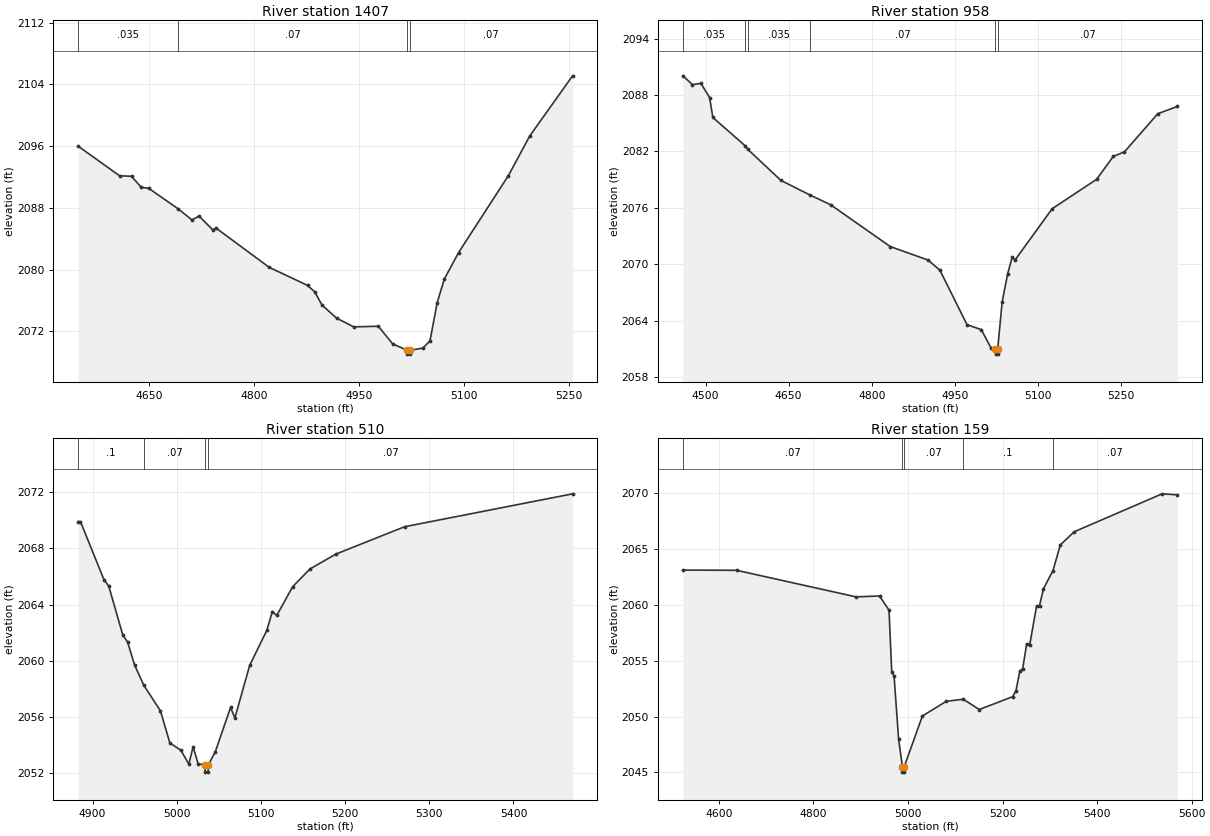
Type RM Length L Ch R = 1,1407,449,449,449
BEGIN DESCRIPTION:
Stream0251 3.0
END DESCRIPTION:
XS GIS Cut Line= 3
      1817810.17     13895512.35      1817925.00     13895075.00
      1817875.01     13894825.03
#Sta/Elev= 30
  4548.1 2095.99  4607.4 2092.15  4624.5 2092.09  4638.4 2090.65  4648.8 2090.54
  4691.6 2087.84  4710.8 2086.43  4721.1 2086.93  4740.5 2085.16  4745.6 2085.36
  4821.2 2080.30  4876.2 2077.95  4886.5 2077.11  4896.8 2075.41  4917.6 2073.72
  4942.3 2072.58  4977.5 2072.66  4997.7 2070.39  5018.7 2069.55  5018.9 2069.05
  5022.4 2069.05  5022.7 2069.55  5041.1 2069.83  5051.3 2070.77  5061.5 2075.69
  5071.7 2078.76  5092.1 2082.20  5163.4 2092.17  5194.0 2097.32  5255.2 2105.10
#Mann=4,-1,0
  4548.1   0.035       0  4691.6    0.07       0  5018.7    0.05       0
  5022.7    0.07       0
Bank Sta=5018.7,5022.7
Exp/Cntr=0.3,0.1

Type RM Length L Ch R = 1,958,448,448,448
BEGIN DESCRIPTION:
Stream0251 2.0
END DESCRIPTION:
XS GIS Cut Line= 3
      1818052.54     13895586.38      1818325.00     13895125.00
      1818296.06     13894769.70
#Sta/Elev= 30
  4459.3 2090.05  4476.2 2089.12  4491.8 2089.24  4507.4 2087.74  4513.2 2085.62
  4571.3 2082.62  4576.1 2082.24  4636.1 2078.92  4688.2 2077.38  4725.9 2076.33
  4833.2 2071.89  4901.5 2070.45  4923.0 2069.37  4971.9 2063.57  4997.6 2063.05
  5015.2 2061.10  5023.2 2060.94  5023.5 2060.44  5027.0 2060.44  5027.2 2060.94
  5035.3 2065.99  5045.3 2069.00  5053.5 2070.77  5058.5 2070.45  5125.6 2075.91
  5205.8 2079.04  5235.9 2081.48  5256.0 2081.96  5316.2 2086.02  5351.6 2086.79
#Mann=6,-1,0
  4459.3   0.035       0  4571.3    0.07       0  4576.1   0.035       0
  4688.2    0.07       0  5023.2    0.05       0  5027.2    0.07       0
Bank Sta=5023.2,5027.2
Exp/Cntr=0.3,0.1

Type RM Length L Ch R = 1,510,351,351,351
BEGIN DESCRIPTION:
Stream0251 1.0
END DESCRIPTION:
XS GIS Cut Line= 3
      1818625.01     13895474.98      1818675.00     13895375.00
      1818576.21     13894909.75
#Sta/Elev= 30
  4882.8 2069.90  4885.6 2069.90  4913.5 2065.77  4919.1 2065.33  4935.9 2061.83
  4941.5 2061.35  4949.9 2059.70  4960.7 2058.28  4980.6 2056.44  4991.8 2054.16
  5004.8 2053.65  5014.3 2052.66  5019.4 2053.89  5025.3 2052.69  5033.5 2052.59
  5033.7 2052.09  5037.2 2052.09  5037.5 2052.59  5045.7 2053.53  5063.9 2056.69
  5069.0 2055.94  5086.6 2059.68  5107.0 2062.18  5113.5 2063.51  5118.7 2063.23
  5137.7 2065.28  5158.1 2066.53  5188.8 2067.59  5270.6 2069.54  5470.2 2071.88
#Mann=4,-1,0
  4882.8     0.1       0  4960.7    0.07       0  5033.5    0.05       0
  5037.5    0.07       0
Bank Sta=5033.5,5037.5
Exp/Cntr=0.3,0.1

Type RM Length L Ch R = 1,159,0,0,0
BEGIN DESCRIPTION:
Stream0251 0.0
END DESCRIPTION:
XS GIS Cut Line= 3
      1819025.02     13895997.54      1818948.46     13895386.91
      1818694.13     13895039.45
#Sta/Elev= 30
  4523.9 2063.12  4637.3 2063.10  4890.0 2060.72  4939.7 2060.80  4959.8 2059.53
  4965.5 2054.01  4970.5 2053.63  4980.0 2048.01  4988.1 2045.52  4988.3 2045.02
  4991.8 2045.02  4992.1 2045.52  5030.4 2050.05  5080.8 2051.36  5116.9 2051.55
  5150.7 2050.63  5221.4 2051.78  5228.4 2052.31  5236.5 2054.07  5242.6 2054.29
  5251.1 2056.53  5257.3 2056.40  5272.0 2059.90  5278.2 2059.94  5286.6 2061.45
  5306.7 2063.08  5322.2 2065.37  5351.5 2066.55  5537.5 2069.95  5569.9 2069.86
#Mann=5,-1,0
  4523.9    0.07       0  4988.1    0.05       0  4992.1    0.07       0
  5116.9     0.1       0  5306.7    0.07       0
Bank Sta=4988.1,4992.1
Exp/Cntr=0.3,0.1

Chan Stop Cuts=-1