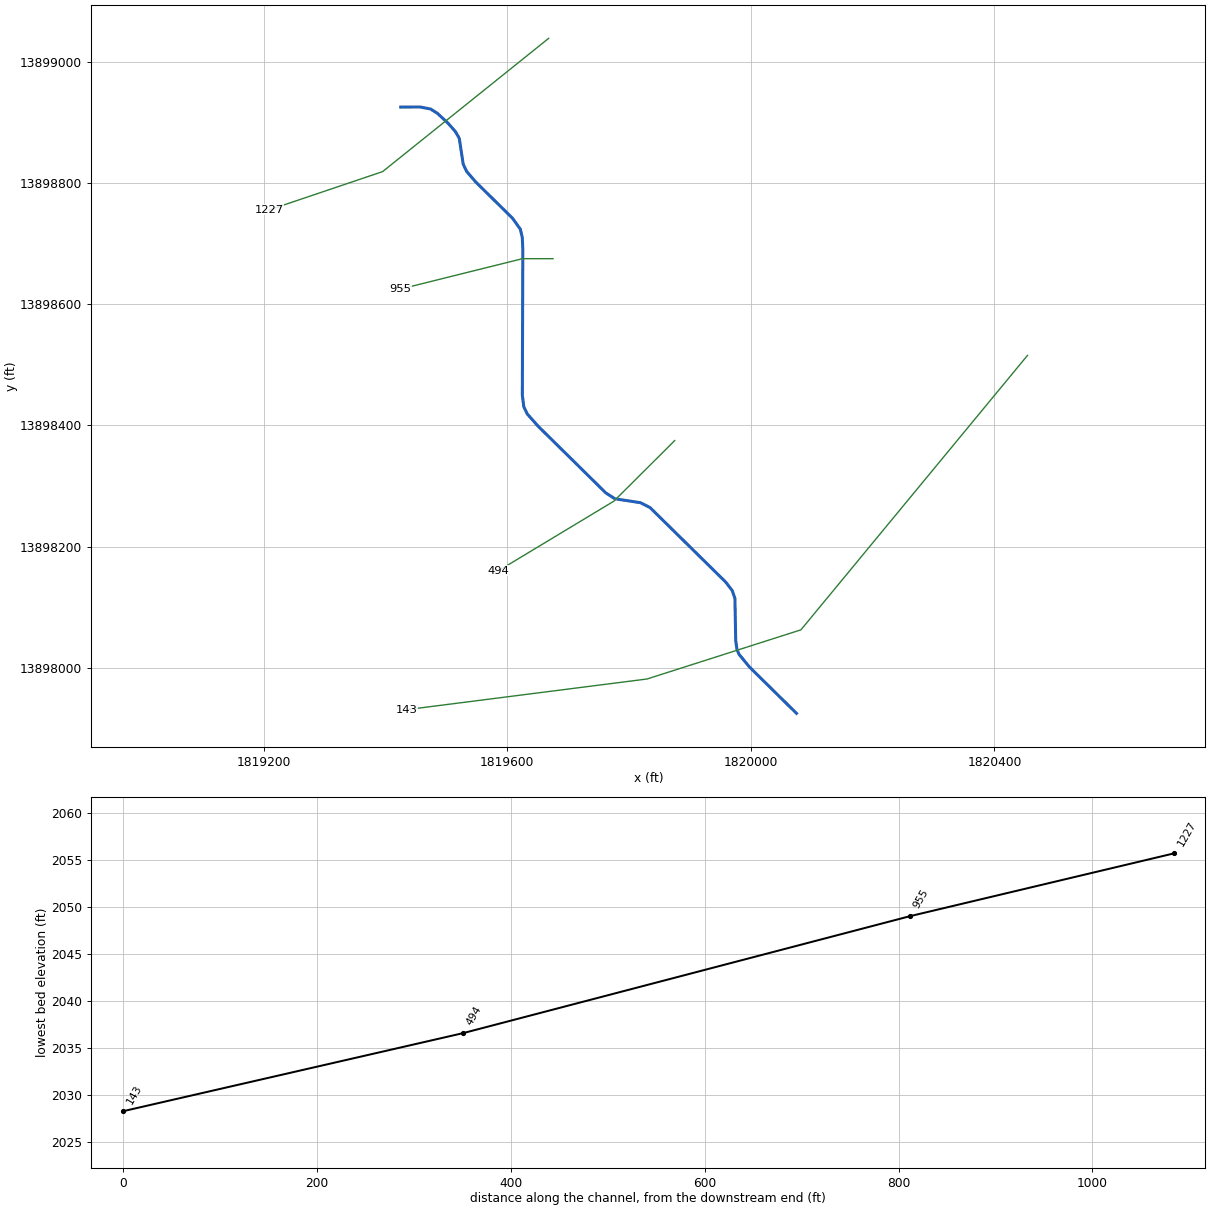
--- Stream0252.prj (project) ---

Proj Title=Stream0252 Base Level Engineering
Current Plan=p01
Default Exp/Contr=0.3,0.1
English Units
Geom File=g01
Flow File=f01
Plan File=p01
BEGIN DESCRIPTION:
Stream0252
END DESCRIPTION:

--- Stream0252.p01 (plan) ---

Plan Title=Multiple Run
Short Identifier=Multiple
Geom File=g01
Flow File=f01
Subcritical Flow
K Sum by GR= 0
Std Step Tol= 0.01
Critical Tol= 0.01
Num of Std Step Trials= 20
Max Error Tol= 0.3
Flow Tol Ratio= 0.001
Split Flow NTrial= 30
Split Flow Tol= 0.02
Split Flow Ratio= 0.02
Log Output Level= 0
Friction Slope Method= 1
Unsteady Friction Slope Method= 2
Unsteady Bridges Friction Slope Method= 1
Parabolic Critical Depth
Global Vel Dist=  1 , 1 , 1
Global Log Level= 0
CheckData=True
Encroach Param= -1, 0, 0, 0
BEGIN DESCRIPTION:
Multiple Run
END DESCRIPTION:

--- Stream0252.f01 (steady flow) ---

Flow Title=Multiple
Number of Profiles=7
Profile Names=10-year,25-year,50-year,1pct_min,100-year,1pct_plu,500-year
River Rch & RM= Stream0252,Reach-1,1227
     605    1012    1392     929    1853    3698    3242
Boundary for River Rch & Prof#=Stream0252,Reach-1,1
Up Type=0
Dn Type=3
Dn Slope=0.005
Boundary for River Rch & Prof#=Stream0252,Reach-1,2
Up Type=0
Dn Type=3
Dn Slope=0.005
Boundary for River Rch & Prof#=Stream0252,Reach-1,3
Up Type=0
Dn Type=3
Dn Slope=0.005
Boundary for River Rch & Prof#=Stream0252,Reach-1,4
Up Type=0
Dn Type=3
Dn Slope=0.005
Boundary for River Rch & Prof#=Stream0252,Reach-1,5
Up Type=0
Dn Type=3
Dn Slope=0.005
Boundary for River Rch & Prof#=Stream0252,Reach-1,6
Up Type=0
Dn Type=3
Dn Slope=0.005
Boundary for River Rch & Prof#=Stream0252,Reach-1,7
Up Type=0
Dn Type=3
Dn Slope=0.005

--- Stream0252.g01 (geometry) ---

Geom Title=Existing Conditions

River Reach=Stream0252,Reach-1
Reach XY= 30
      1819425.00     13898925.00      1819457.05     13898925.15
      1819473.97     13898921.86      1819485.25     13898914.68
      1819502.27     13898898.85      1819514.44     13898884.97
      1819521.14     13898873.54      1819527.52     13898831.07
      1819533.17     13898818.97      1819548.07     13898801.56
      1819608.54     13898741.75      1819621.45     13898723.53
      1819624.61     13898709.84      1819625.49     13898690.20
      1819624.70     13898449.88      1819627.06     13898430.85
      1819632.81     13898418.81      1819651.16     13898398.12
      1819761.79     13898288.63      1819776.65     13898278.98
      1819818.95     13898272.47      1819834.68     13898264.22
      1819958.54     13898141.75      1819969.48     13898127.43
      1819973.84     13898114.52      1819975.13     13898045.05
      1819977.12     13898030.88      1819980.46     13898022.55
      1819997.77     13898001.43      1820075.00     13897925.00

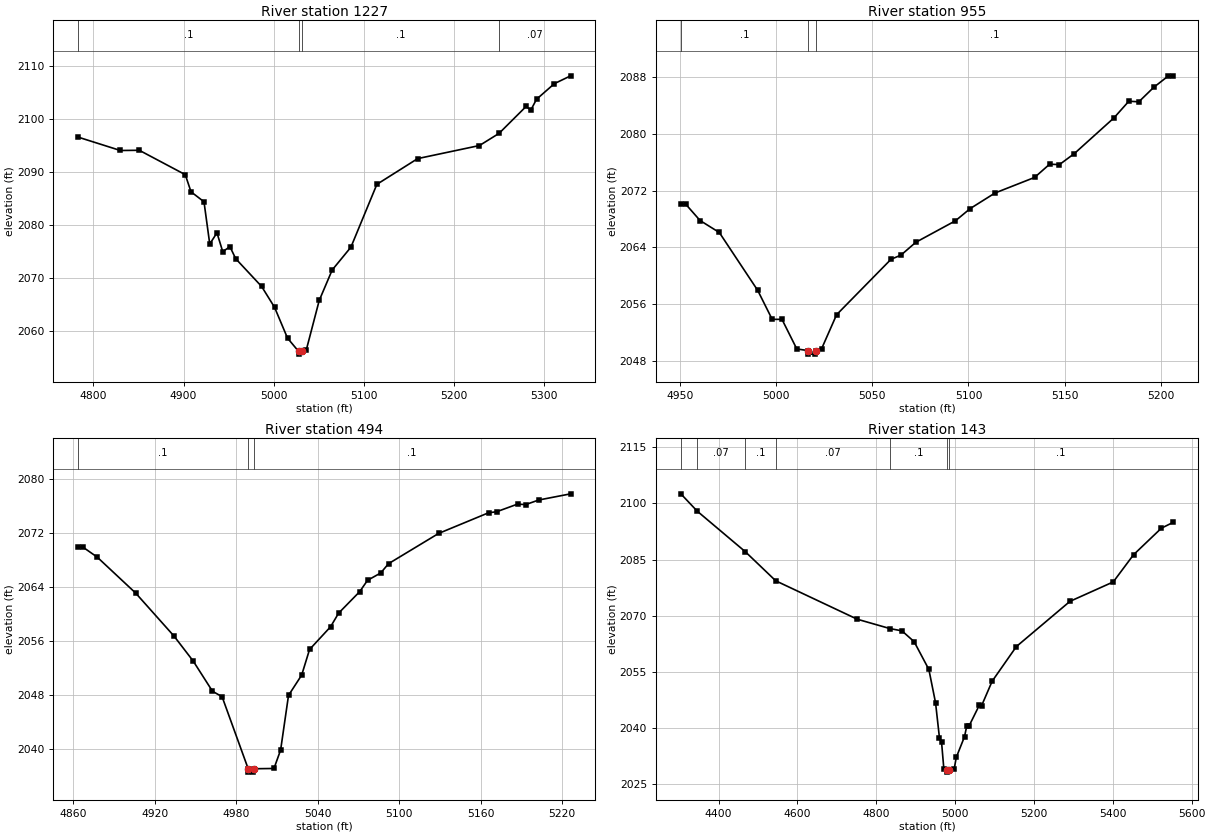
Type RM Length L Ch R = 1,1227,272,272,272
BEGIN DESCRIPTION:
Stream0252 3.0
END DESCRIPTION:
XS GIS Cut Line= 3
      1819667.95     13899038.42      1819395.20     13898818.57
      1819209.13     13898755.47
#Sta/Elev= 30
  4782.9 2096.65  4829.9 2094.12  4850.9 2094.16  4901.9 2089.56  4908.3 2086.32
  4922.7 2084.44  4929.1 2076.46  4937.1 2078.58  4943.5 2075.02  4951.5 2075.96
  4957.9 2073.69  4986.7 2068.44  5001.0 2064.52  5015.4 2058.70  5027.8 2056.17
  5028.1 2055.67  5031.8 2056.17  5036.2 2056.42  5050.6 2065.80  5065.0 2071.56
  5085.8 2075.87  5114.6 2087.73  5159.9 2092.59  5228.5 2095.06  5250.2 2097.35
  5280.2 2102.43  5285.5 2101.75  5291.8 2103.79  5311.6 2106.74  5329.7 2108.22
#Mann=4,-1,0
  4782.9     0.1       0  5027.8    0.05       0  5031.8     0.1       0
  5250.2    0.07       0
Bank Sta=5027.8,5031.8
Exp/Cntr=0.3,0.1

Type RM Length L Ch R = 1,955,461,461,461
BEGIN DESCRIPTION:
Stream0252 2.0
END DESCRIPTION:
XS GIS Cut Line= 3
      1819675.04     13898675.00      1819625.00     13898675.00
      1819425.00     13898625.00
#Sta/Elev= 30
  4950.4 2070.09  4952.9 2070.09  4960.4 2067.78  4970.4 2066.10  4990.4 2057.95
  4997.9 2053.89  5003.0 2053.89  5010.7 2049.73  5016.5 2049.50  5016.7 2049.00
  5020.2 2049.00  5020.5 2049.50  5023.6 2049.75  5031.4 2054.54  5059.7 2062.33
  5064.9 2062.92  5072.6 2064.72  5093.2 2067.74  5100.9 2069.46  5113.8 2071.65
  5134.4 2073.84  5142.2 2075.70  5147.3 2075.64  5155.1 2077.20  5175.7 2082.22
  5183.4 2084.55  5188.6 2084.47  5196.3 2086.49  5204.0 2088.12  5206.6 2088.12
#Mann=3,-1,0
  4950.4     0.1       0  5016.5    0.05       0  5020.5     0.1       0
Bank Sta=5016.5,5020.5
Exp/Cntr=0.3,0.1

Type RM Length L Ch R = 1,494,351,351,351
BEGIN DESCRIPTION:
Stream0252 1.0
END DESCRIPTION:
XS GIS Cut Line= 3
      1819874.99     13898374.99      1819775.00     13898275.00
      1819585.60     13898160.37
#Sta/Elev= 30
  4863.4 2069.89  4866.9 2069.89  4877.5 2068.40  4905.8 2063.08  4934.1 2056.70
  4948.2 2053.01  4962.4 2048.54  4969.5 2047.72  4988.7 2037.06  4988.9 2036.56
  4992.4 2036.56  4992.7 2037.06  5007.7 2037.10  5012.6 2039.84  5018.4 2047.92
  5028.1 2050.93  5033.9 2054.72  5049.4 2058.09  5055.3 2060.10  5070.8 2063.28
  5076.6 2064.96  5086.3 2066.05  5092.1 2067.43  5128.9 2071.90  5165.8 2074.97
  5171.6 2075.11  5187.1 2076.25  5193.0 2076.17  5202.6 2076.85  5226.2 2077.77
#Mann=3,-1,0
  4863.4     0.1       0  4988.7    0.05       0  4992.7     0.1       0
Bank Sta=4988.7,4992.7
Exp/Cntr=0.3,0.1

Type RM Length L Ch R = 1,143,0,0,0
BEGIN DESCRIPTION:
Stream0252 0.0
END DESCRIPTION:
XS GIS Cut Line= 4
      1820454.39     13898515.53      1820082.23     13898062.78
      1819829.53     13897981.71      1819434.53     13897931.10
#Sta/Elev= 30
  4304.1 2102.55  4345.7 2097.92  4467.7 2087.09  4544.8 2079.33  4751.7 2069.07
  4835.1 2066.56  4865.0 2065.97  4895.9 2063.08  4933.3 2055.66  4950.3 2046.75
  4960.1 2037.48  4965.4 2036.38  4971.3 2029.13  4979.8 2028.75  4980.0 2028.25
  4983.8 2028.75  4997.5 2029.05  5002.8 2032.17  5023.8 2037.73  5029.6 2040.65
  5034.9 2040.49  5061.7 2046.20  5067.0 2045.96  5093.9 2052.53  5155.3 2061.77
  5291.2 2073.84  5401.1 2079.03  5452.5 2086.28  5523.1 2093.37  5553.8 2094.97
#Mann=7,-1,0
  4304.1     0.1       0  4345.7    0.07       0  4467.7     0.1       0
  4544.8    0.07       0  4835.1     0.1       0  4979.8    0.05       0
  4983.8     0.1       0
Bank Sta=4979.8,4983.8
Exp/Cntr=0.3,0.1

Chan Stop Cuts=-1