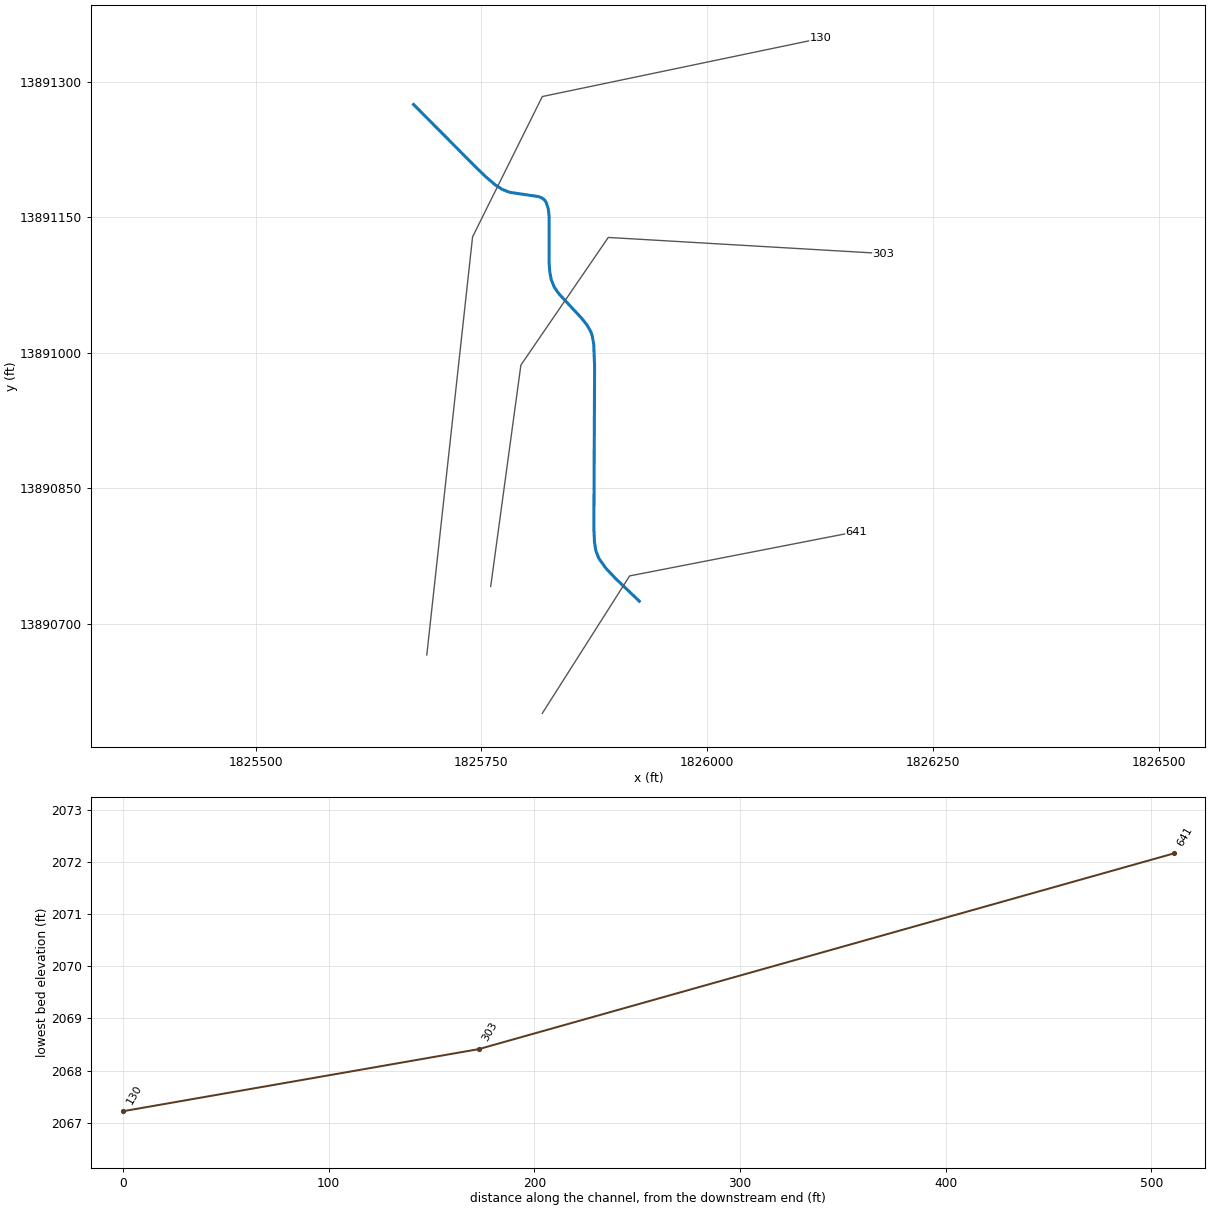
--- Stream0254.prj (project) ---

Proj Title=Stream0254 Base Level Engineering
Current Plan=p01
Default Exp/Contr=0.3,0.1
English Units
Geom File=g01
Flow File=f01
Plan File=p01
BEGIN DESCRIPTION:
Stream0254
END DESCRIPTION:

--- Stream0254.p01 (plan) ---

Plan Title=Multiple Run
Short Identifier=Multiple
Geom File=g01
Flow File=f01
Subcritical Flow
K Sum by GR= 0
Std Step Tol= 0.01
Critical Tol= 0.01
Num of Std Step Trials= 20
Max Error Tol= 0.3
Flow Tol Ratio= 0.001
Split Flow NTrial= 30
Split Flow Tol= 0.02
Split Flow Ratio= 0.02
Log Output Level= 0
Friction Slope Method= 1
Unsteady Friction Slope Method= 2
Unsteady Bridges Friction Slope Method= 1
Parabolic Critical Depth
Global Vel Dist=  1 , 1 , 1
Global Log Level= 0
CheckData=True
Encroach Param= -1, 0, 0, 0
BEGIN DESCRIPTION:
Multiple Run
END DESCRIPTION:

--- Stream0254.f01 (steady flow) ---

Flow Title=Multiple
Number of Profiles=7
Profile Names=10-year,25-year,50-year,1pct_min,100-year,1pct_plu,500-year
River Rch & RM= Stream0254,Reach-1,641
    1140    1953    2728    1841    3674    7330    6587
Boundary for River Rch & Prof#=Stream0254,Reach-1,1
Up Type=0
Dn Type=3
Dn Slope=0.005
Boundary for River Rch & Prof#=Stream0254,Reach-1,2
Up Type=0
Dn Type=3
Dn Slope=0.005
Boundary for River Rch & Prof#=Stream0254,Reach-1,3
Up Type=0
Dn Type=3
Dn Slope=0.005
Boundary for River Rch & Prof#=Stream0254,Reach-1,4
Up Type=0
Dn Type=3
Dn Slope=0.005
Boundary for River Rch & Prof#=Stream0254,Reach-1,5
Up Type=0
Dn Type=3
Dn Slope=0.005
Boundary for River Rch & Prof#=Stream0254,Reach-1,6
Up Type=0
Dn Type=3
Dn Slope=0.005
Boundary for River Rch & Prof#=Stream0254,Reach-1,7
Up Type=0
Dn Type=3
Dn Slope=0.005

--- Stream0254.g01 (geometry) ---

Geom Title=Existing Conditions

River Reach=Stream0254,Reach-1
Reach XY= 30
      1825925.00     13890725.00      1825899.11     13890749.71
      1825887.92     13890761.49      1825880.14     13890772.41
      1825876.89     13890780.78      1825875.36     13890790.15
      1825874.64     13890804.85      1825875.45     13890985.19
      1825874.48     13891009.79      1825872.74     13891019.07
      1825871.22     13891023.44      1825866.86     13891031.06
      1825861.22     13891038.15      1825835.91     13891065.41
      1825830.84     13891072.75      1825827.39     13891081.06
      1825825.72     13891090.40      1825825.09     13891100.19
      1825825.13     13891150.13      1825824.20     13891159.11
      1825821.85     13891166.67      1825819.76     13891169.54
      1825816.85     13891171.61      1825813.28     13891173.02
      1825781.54     13891177.72      1825773.11     13891180.99
      1825765.62     13891185.85      1825755.08     13891194.79
      1825744.93     13891204.57      1825675.00     13891275.00

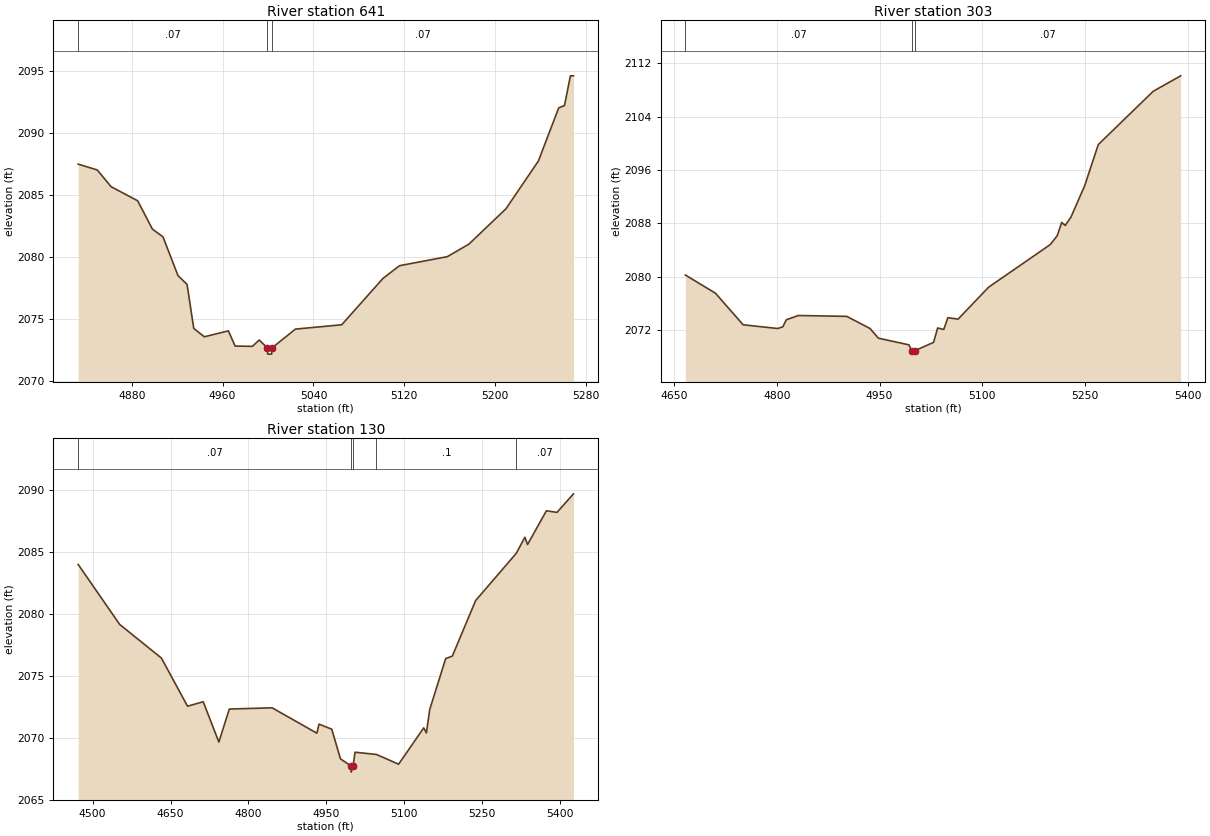
Type RM Length L Ch R = 1,641,338,338,338
BEGIN DESCRIPTION:
Stream0254 2.0
END DESCRIPTION:
XS GIS Cut Line= 3
      1825817.50     13890600.80      1825914.22     13890752.99
      1826165.36     13890801.97
#Sta/Elev= 30
  4832.8 2087.50  4849.6 2087.03  4861.8 2085.68  4885.2 2084.54  4898.2 2082.25
  4907.5 2081.63  4920.7 2078.50  4928.7 2077.79  4934.6 2074.23  4943.9 2073.56
  4965.1 2074.04  4971.0 2072.81  4986.3 2072.79  4992.2 2073.30  4999.5 2072.66
  4999.7 2072.16  5003.2 2072.16  5003.5 2072.66  5024.1 2074.18  5064.9 2074.53
  5101.2 2078.27  5115.8 2079.30  5157.9 2080.03  5176.9 2081.04  5209.5 2083.89
  5238.1 2087.75  5256.0 2092.04  5261.1 2092.23  5266.3 2094.63  5269.0 2094.63
#Mann=3,-1,0
  4832.8    0.07       0  4999.5    0.05       0  5003.5    0.07       0
Bank Sta=4999.5,5003.5
Exp/Cntr=0.3,0.1

Type RM Length L Ch R = 1,303,173,173,173
BEGIN DESCRIPTION:
Stream0254 1.0
END DESCRIPTION:
XS GIS Cut Line= 4
      1825760.42     13890741.39      1825793.82     13890986.42
      1825890.60     13891127.78      1826195.07     13891109.94
#Sta/Elev= 30
  4666.3 2080.27  4710.3 2077.54  4750.7 2072.81  4801.1 2072.25  4808.7 2072.51
  4813.8 2073.56  4831.4 2074.20  4902.1 2074.07  4936.1 2072.25  4948.3 2070.80
  4993.0 2069.80  4997.1 2068.91  4997.3 2068.41  5000.8 2068.41  5001.1 2068.91
  5028.9 2070.17  5034.9 2072.33  5043.8 2072.11  5049.8 2073.87  5064.8 2073.66
  5109.4 2078.45  5199.5 2084.84  5209.5 2086.15  5216.2 2088.15  5221.2 2087.70
  5229.6 2088.94  5249.6 2093.63  5269.6 2099.83  5349.8 2107.81  5389.9 2110.13
#Mann=3,-1,0
  4666.3    0.07       0  4997.1    0.05       0  5001.1    0.07       0
Bank Sta=4997.1,5001.1
Exp/Cntr=0.3,0.1

Type RM Length L Ch R = 1,130,0,0,0
BEGIN DESCRIPTION:
Stream0254 0.0
END DESCRIPTION:
XS GIS Cut Line= 4
      1825689.65     13890665.52      1825740.34     13891128.43
      1825817.55     13891283.78      1826126.03     13891348.23
#Sta/Elev= 30
  4472.1 2084.01  4552.1 2079.16  4632.5 2076.44  4682.8 2072.55  4713.0 2072.91
  4743.2 2069.65  4763.3 2072.32  4845.8 2072.42  4932.0 2070.37  4936.2 2071.10
  4960.7 2070.69  4977.5 2068.29  4997.9 2067.72  4998.1 2067.22  5001.9 2067.72
  5005.5 2068.83  5046.7 2068.65  5089.5 2067.86  5137.9 2070.80  5143.0 2070.39
  5149.5 2072.29  5180.2 2076.40  5193.0 2076.60  5237.9 2081.09  5316.2 2084.91
  5332.8 2086.21  5337.9 2085.62  5374.3 2088.35  5394.7 2088.22  5426.4 2089.72
#Mann=5,-1,0
  4472.1    0.07       0  4997.9    0.05       0  5001.9    0.07       0
  5046.7     0.1       0  5316.2    0.07       0
Bank Sta=4997.9,5001.9
Exp/Cntr=0.3,0.1

Chan Stop Cuts=-1