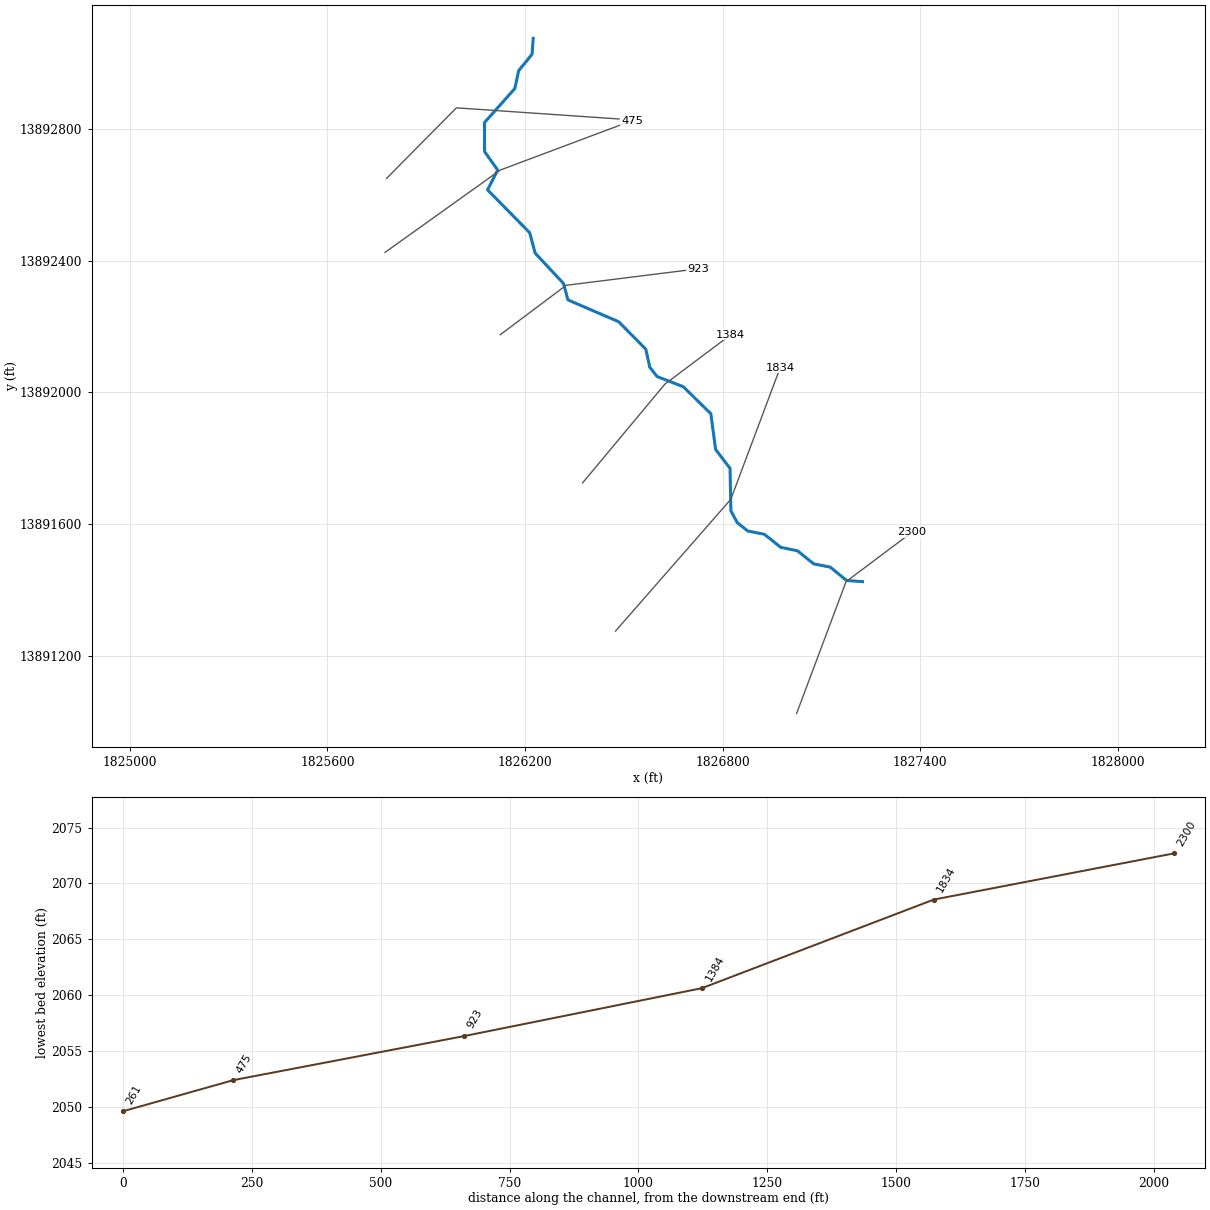
--- Stream0255.prj (project) ---

Proj Title=Stream0255 Base Level Engineering
Current Plan=p01
Default Exp/Contr=0.3,0.1
English Units
Geom File=g01
Flow File=f01
Plan File=p01
BEGIN DESCRIPTION:
Stream0255
END DESCRIPTION:

--- Stream0255.p01 (plan) ---

Plan Title=Multiple Run
Short Identifier=Multiple
Geom File=g01
Flow File=f01
Subcritical Flow
K Sum by GR= 0
Std Step Tol= 0.01
Critical Tol= 0.01
Num of Std Step Trials= 20
Max Error Tol= 0.3
Flow Tol Ratio= 0.001
Split Flow NTrial= 30
Split Flow Tol= 0.02
Split Flow Ratio= 0.02
Log Output Level= 0
Friction Slope Method= 1
Unsteady Friction Slope Method= 2
Unsteady Bridges Friction Slope Method= 1
Parabolic Critical Depth
Global Vel Dist=  1 , 1 , 1
Global Log Level= 0
CheckData=True
Encroach Param= -1, 0, 0, 0
BEGIN DESCRIPTION:
Multiple Run
END DESCRIPTION:

--- Stream0255.f01 (steady flow) ---

Flow Title=Multiple
Number of Profiles=7
Profile Names=10-year,25-year,50-year,1pct_min,100-year,1pct_plu,500-year
River Rch & RM= Stream0255,Reach-1,2300
    1400    2440    3448    2354    4697    9373    8621
Boundary for River Rch & Prof#=Stream0255,Reach-1,1
Up Type=0
Dn Type=3
Dn Slope=0.005
Boundary for River Rch & Prof#=Stream0255,Reach-1,2
Up Type=0
Dn Type=3
Dn Slope=0.005
Boundary for River Rch & Prof#=Stream0255,Reach-1,3
Up Type=0
Dn Type=3
Dn Slope=0.005
Boundary for River Rch & Prof#=Stream0255,Reach-1,4
Up Type=0
Dn Type=3
Dn Slope=0.005
Boundary for River Rch & Prof#=Stream0255,Reach-1,5
Up Type=0
Dn Type=3
Dn Slope=0.005
Boundary for River Rch & Prof#=Stream0255,Reach-1,6
Up Type=0
Dn Type=3
Dn Slope=0.005
Boundary for River Rch & Prof#=Stream0255,Reach-1,7
Up Type=0
Dn Type=3
Dn Slope=0.005

--- Stream0255.g01 (geometry) ---

Geom Title=Existing Conditions

River Reach=Stream0255,Reach-1
Reach XY= 30
      1827225.00     13891425.00      1827176.49     13891428.60
      1827127.25     13891469.05      1827076.72     13891479.14
      1827027.20     13891518.92      1826976.72     13891529.16
      1826927.16     13891568.88      1826876.39     13891578.85
      1826844.44     13891604.45      1826825.34     13891640.04
      1826822.73     13891769.06      1826778.86     13891826.60
      1826764.49     13891934.81      1826681.05     13892016.84
      1826601.16     13892047.86      1826578.89     13892076.43
      1826566.84     13892131.05      1826484.70     13892214.24
      1826330.61     13892280.59      1826316.70     13892330.74
      1826230.87     13892422.72      1826214.22     13892484.68
      1826086.24     13892615.00      1826117.19     13892674.90
      1826077.35     13892730.89      1826076.97     13892819.10
      1826169.17     13892922.70      1826180.97     13892977.24
      1826221.40     13893026.49      1826225.00     13893075.00

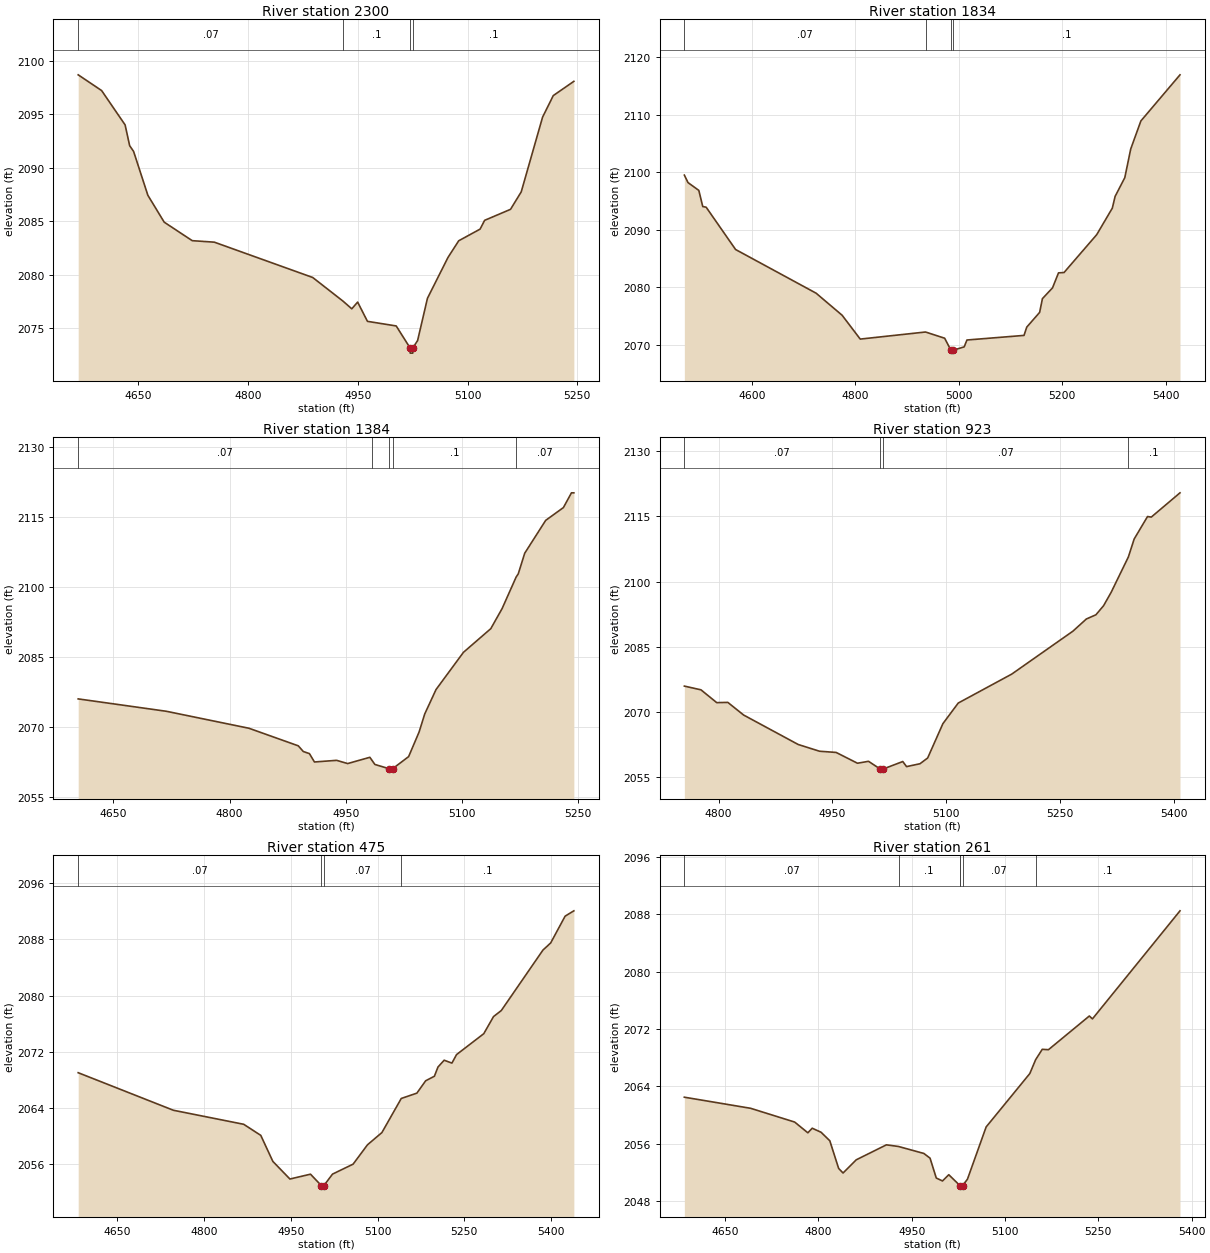
Type RM Length L Ch R = 1,2300,466,466,466
BEGIN DESCRIPTION:
Stream0255 5.0
END DESCRIPTION:
XS GIS Cut Line= 3
      1827025.00     13891025.00      1827175.00     13891425.00
      1827375.00     13891575.00
#Sta/Elev= 30
  4568.1 2098.70  4600.1 2097.23  4632.2 2094.02  4638.4 2092.08  4643.8 2091.54
  4663.3 2087.44  4685.6 2084.93  4723.9 2083.20  4754.1 2083.06  4888.5 2079.76
  4929.9 2077.55  4941.9 2076.83  4949.9 2077.46  4963.3 2075.66  5002.6 2075.23
  5021.4 2073.19  5021.7 2072.69  5025.2 2072.69  5025.4 2073.19  5031.8 2073.86
  5045.3 2077.82  5073.4 2081.64  5088.0 2083.19  5117.2 2084.28  5123.4 2085.10
  5158.8 2086.13  5173.4 2087.76  5202.6 2094.75  5217.2 2096.76  5245.3 2098.09
#Mann=4,-1,0
  4568.1    0.07       0  4929.9     0.1       0  5021.4    0.05       0
  5025.4     0.1       0
Bank Sta=5021.4,5025.4
Exp/Cntr=0.3,0.1

Type RM Length L Ch R = 1,1834,450,450,450
BEGIN DESCRIPTION:
Stream0255 4.0
END DESCRIPTION:
XS GIS Cut Line= 3
      1826475.02     13891275.03      1826825.00     13891675.00
      1826975.01     13892075.02
#Sta/Elev= 30
  4469.1 2099.50  4476.2 2098.20  4497.1 2096.84  4504.7 2094.04  4511.3 2093.92
  4568.2 2086.57  4723.9 2078.98  4774.2 2075.15  4809.3 2071.00  4935.6 2072.23
  4972.6 2071.15  4984.7 2069.06  4985.0 2068.56  4988.9 2069.06  5010.4 2069.65
  5015.7 2070.84  5126.1 2071.64  5131.4 2073.08  5156.3 2075.64  5161.7 2078.03
  5181.2 2079.90  5192.8 2082.51  5203.5 2082.57  5266.7 2089.15  5296.9 2093.76
  5302.3 2095.80  5321.0 2099.05  5332.5 2104.04  5352.1 2108.91  5427.8 2116.93
#Mann=4,-1,0
  4469.1    0.07       0  4935.6     0.1       0  4984.7    0.05       0
  4988.9     0.1       0
Bank Sta=4984.7,4988.9
Exp/Cntr=0.3,0.1

Type RM Length L Ch R = 1,1384,461,461,461
BEGIN DESCRIPTION:
Stream0255 3.0
END DESCRIPTION:
XS GIS Cut Line= 3
      1826374.99     13891724.99      1826625.00     13892025.00
      1826824.98     13892174.98
#Sta/Elev= 30
  4604.4 2076.11  4718.3 2073.46  4825.1 2069.82  4888.8 2066.06  4895.3 2064.84
  4903.2 2064.39  4909.7 2062.60  4938.3 2062.95  4952.6 2062.26  4981.3 2063.60
  4984.1 2062.94  4987.8 2062.07  5006.4 2061.14  5006.6 2060.64  5010.3 2060.64
  5010.6 2061.14  5031.4 2063.75  5044.9 2069.01  5052.2 2072.88  5066.8 2078.11
  5102.2 2086.08  5137.6 2091.16  5152.2 2095.46  5170.3 2102.20  5173.1 2102.91
  5181.4 2107.31  5208.5 2114.35  5231.4 2117.09  5241.8 2120.25  5244.9 2120.25
#Mann=5,-1,0
  4604.4    0.07       0  4984.1     0.1       0  5006.4    0.05       0
  5010.6     0.1       0  5170.3    0.07       0
Bank Sta=5006.4,5010.6
Exp/Cntr=0.3,0.1

Type RM Length L Ch R = 1,923,448,448,448
BEGIN DESCRIPTION:
Stream0255 2.0
END DESCRIPTION:
XS GIS Cut Line= 3
      1826124.99     13892174.99      1826325.00     13892325.00
      1826724.97     13892375.00
#Sta/Elev= 30
  4754.8 2075.93  4776.7 2075.07  4797.5 2072.12  4812.1 2072.18  4832.9 2069.27
  4904.8 2062.49  4932.9 2060.94  4954.8 2060.66  4982.9 2058.18  4997.5 2058.62
  5012.7 2056.86  5013.0 2056.36  5017.0 2056.86  5042.6 2058.57  5047.6 2057.40
  5065.3 2058.06  5075.4 2059.38  5095.5 2067.29  5115.7 2072.03  5186.2 2078.69
  5266.8 2088.57  5284.5 2091.37  5297.1 2092.34  5307.2 2094.43  5317.2 2097.52
  5339.9 2105.66  5347.5 2109.78  5365.1 2114.95  5370.1 2114.83  5407.9 2120.41
#Mann=4,-1,0
  4754.8    0.07       0  5012.7    0.05       0  5017.0    0.07       0
  5339.9     0.1       0
Bank Sta=5012.7,5017
Exp/Cntr=0.3,0.1

Type RM Length L Ch R = 1,475,214,214,214
BEGIN DESCRIPTION:
Stream0255 1.0
END DESCRIPTION:
XS GIS Cut Line= 3
      1825775.02     13892425.02      1826125.00     13892675.00
      1826525.01     13892825.00
#Sta/Elev= 30
  4582.3 2069.01  4746.9 2063.66  4868.6 2061.66  4898.1 2060.08  4919.0 2056.37
  4948.5 2053.86  4984.1 2054.55  5002.9 2052.92  5003.2 2052.42  5006.9 2052.42
  5007.2 2052.92  5022.2 2054.56  5057.8 2055.98  5082.7 2058.74  5107.6 2060.48
  5141.1 2065.34  5168.1 2066.10  5183.3 2067.86  5198.4 2068.51  5204.6 2069.82
  5215.3 2070.79  5228.7 2070.38  5236.7 2071.59  5283.8 2074.57  5300.7 2077.01
  5314.1 2077.87  5386.2 2086.49  5399.5 2087.50  5424.5 2091.32  5439.6 2092.08
#Mann=4,-1,0
  4582.3    0.07       0  5002.9    0.05       0  5007.2    0.07       0
  5141.1     0.1       0
Bank Sta=5002.9,5007.2
Exp/Cntr=0.3,0.1

Type RM Length L Ch R = 1,261,0,0,0
BEGIN DESCRIPTION:
Stream0255 0.0
END DESCRIPTION:
XS GIS Cut Line= 3
      1825779.56     13892649.58      1825991.68     13892863.91
      1826485.97     13892830.07
#Sta/Elev= 30
  4584.3 2062.47  4690.9 2060.92  4761.7 2059.00  4782.9 2057.50  4789.9 2058.14
  4804.1 2057.58  4818.2 2056.39  4832.4 2052.53  4839.5 2051.89  4860.7 2053.73
  4909.2 2055.82  4928.7 2055.59  4969.4 2054.62  4979.4 2053.96  4989.4 2051.19
  4999.4 2050.78  5009.5 2051.65  5027.3 2050.15  5027.4 2050.14  5027.7 2049.64
  5031.7 2050.14  5039.5 2051.02  5069.6 2058.32  5139.8 2065.77  5149.2 2067.71
  5159.8 2069.15  5169.8 2069.10  5235.5 2073.80  5240.5 2073.40  5381.3 2088.48
#Mann=6,-1,0
  4584.3    0.07       0  4928.7     0.1       0  5027.3    0.07       0
  5027.4    0.05       0  5031.7    0.07       0  5149.2     0.1       0
Bank Sta=5027.4,5031.7
Exp/Cntr=0.3,0.1

Chan Stop Cuts=-1