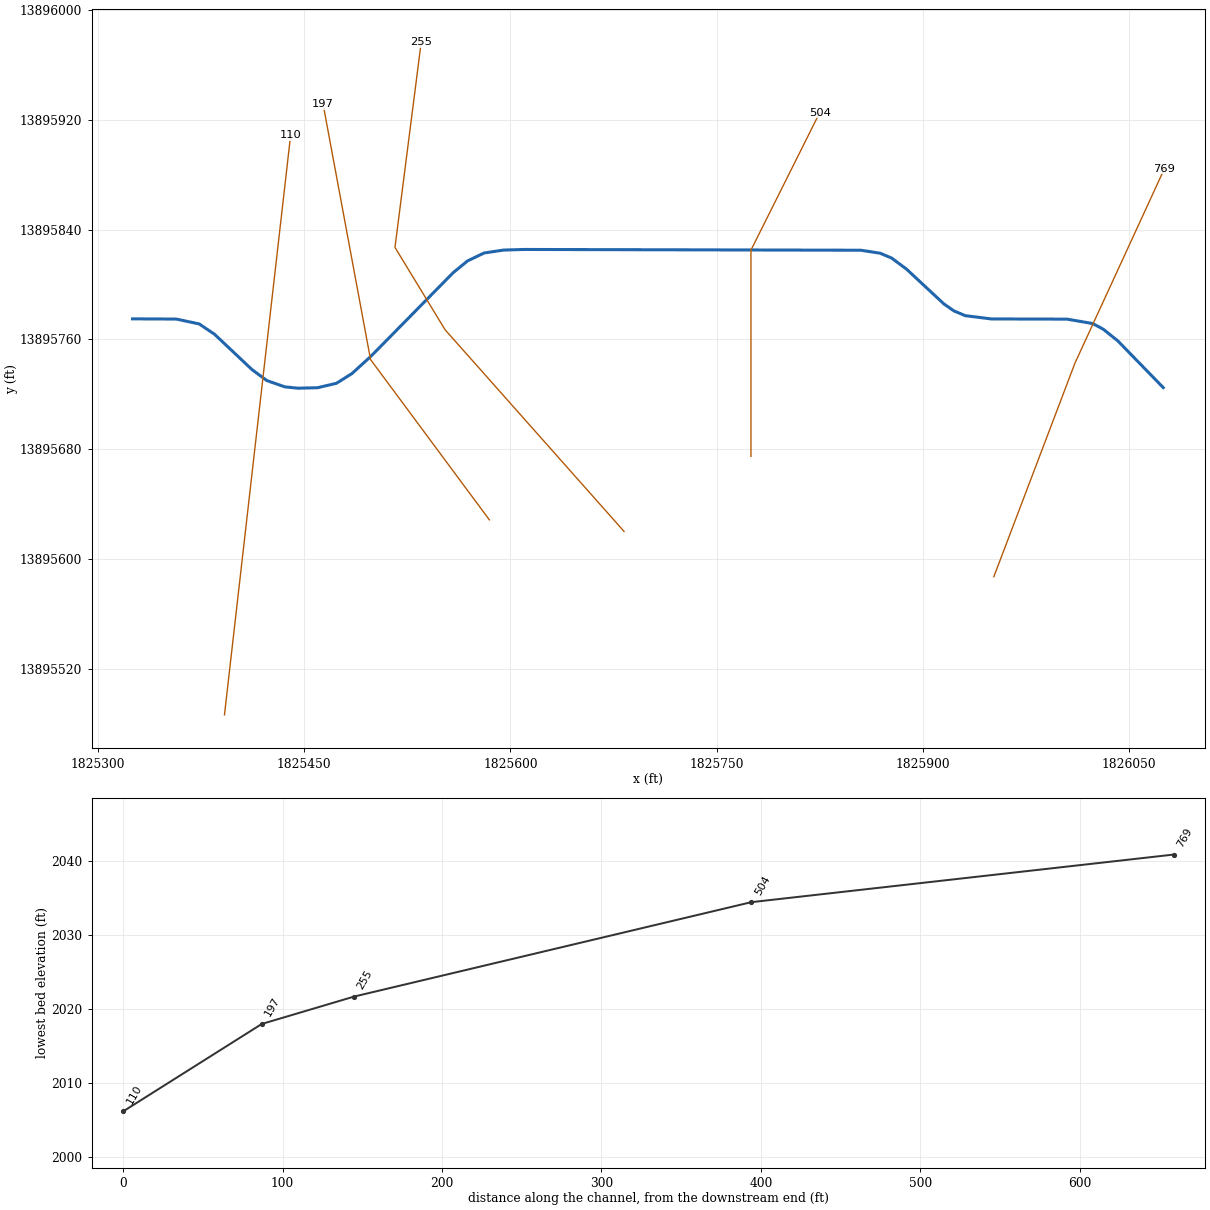
--- Stream0256.prj (project) ---

Proj Title=Stream0256 Base Level Engineering
Current Plan=p01
Default Exp/Contr=0.3,0.1
English Units
Geom File=g01
Flow File=f01
Plan File=p01
BEGIN DESCRIPTION:
Stream0256
END DESCRIPTION:

--- Stream0256.p01 (plan) ---

Plan Title=Multiple Run
Short Identifier=Multiple
Geom File=g01
Flow File=f01
Subcritical Flow
K Sum by GR= 0
Std Step Tol= 0.01
Critical Tol= 0.01
Num of Std Step Trials= 20
Max Error Tol= 0.3
Flow Tol Ratio= 0.001
Split Flow NTrial= 30
Split Flow Tol= 0.02
Split Flow Ratio= 0.02
Log Output Level= 0
Friction Slope Method= 1
Unsteady Friction Slope Method= 2
Unsteady Bridges Friction Slope Method= 1
Parabolic Critical Depth
Global Vel Dist=  1 , 1 , 1
Global Log Level= 0
CheckData=True
Encroach Param= -1, 0, 0, 0
BEGIN DESCRIPTION:
Multiple Run
END DESCRIPTION:

--- Stream0256.f01 (steady flow) ---

Flow Title=Multiple
Number of Profiles=7
Profile Names=10-year,25-year,50-year,1pct_min,100-year,1pct_plu,500-year
River Rch & RM= Stream0256,Reach-1,769
     343     549     734     478     953    1902    1583
Boundary for River Rch & Prof#=Stream0256,Reach-1,1
Up Type=0
Dn Type=3
Dn Slope=0.005
Boundary for River Rch & Prof#=Stream0256,Reach-1,2
Up Type=0
Dn Type=3
Dn Slope=0.005
Boundary for River Rch & Prof#=Stream0256,Reach-1,3
Up Type=0
Dn Type=3
Dn Slope=0.005
Boundary for River Rch & Prof#=Stream0256,Reach-1,4
Up Type=0
Dn Type=3
Dn Slope=0.005
Boundary for River Rch & Prof#=Stream0256,Reach-1,5
Up Type=0
Dn Type=3
Dn Slope=0.005
Boundary for River Rch & Prof#=Stream0256,Reach-1,6
Up Type=0
Dn Type=3
Dn Slope=0.005
Boundary for River Rch & Prof#=Stream0256,Reach-1,7
Up Type=0
Dn Type=3
Dn Slope=0.005

--- Stream0256.g01 (geometry) ---

Geom Title=Existing Conditions

River Reach=Stream0256,Reach-1
Reach XY= 30
      1826075.00     13895725.00      1826042.05     13895758.88
      1826031.32     13895767.50      1826023.60     13895771.61
      1826004.92     13895774.81      1825949.97     13895774.94
      1825930.96     13895777.32      1825922.68     13895780.79
      1825915.37     13895785.89      1825888.15     13895811.22
      1825877.34     13895819.26      1825869.06     13895822.74
      1825854.97     13895824.93      1825609.80     13895825.49
      1825594.98     13895825.04      1825580.86     13895822.93
      1825568.81     13895817.17      1825558.25     13895808.53
      1825498.45     13895747.76      1825484.68     13895735.21
      1825473.37     13895728.12      1825459.67     13895724.91
      1825445.21     13895724.55      1825435.69     13895725.57
      1825422.76     13895730.09      1825411.85     13895738.17
      1825384.60     13895763.86      1825373.51     13895771.31
      1825356.81     13895774.86      1825325.00     13895775.00

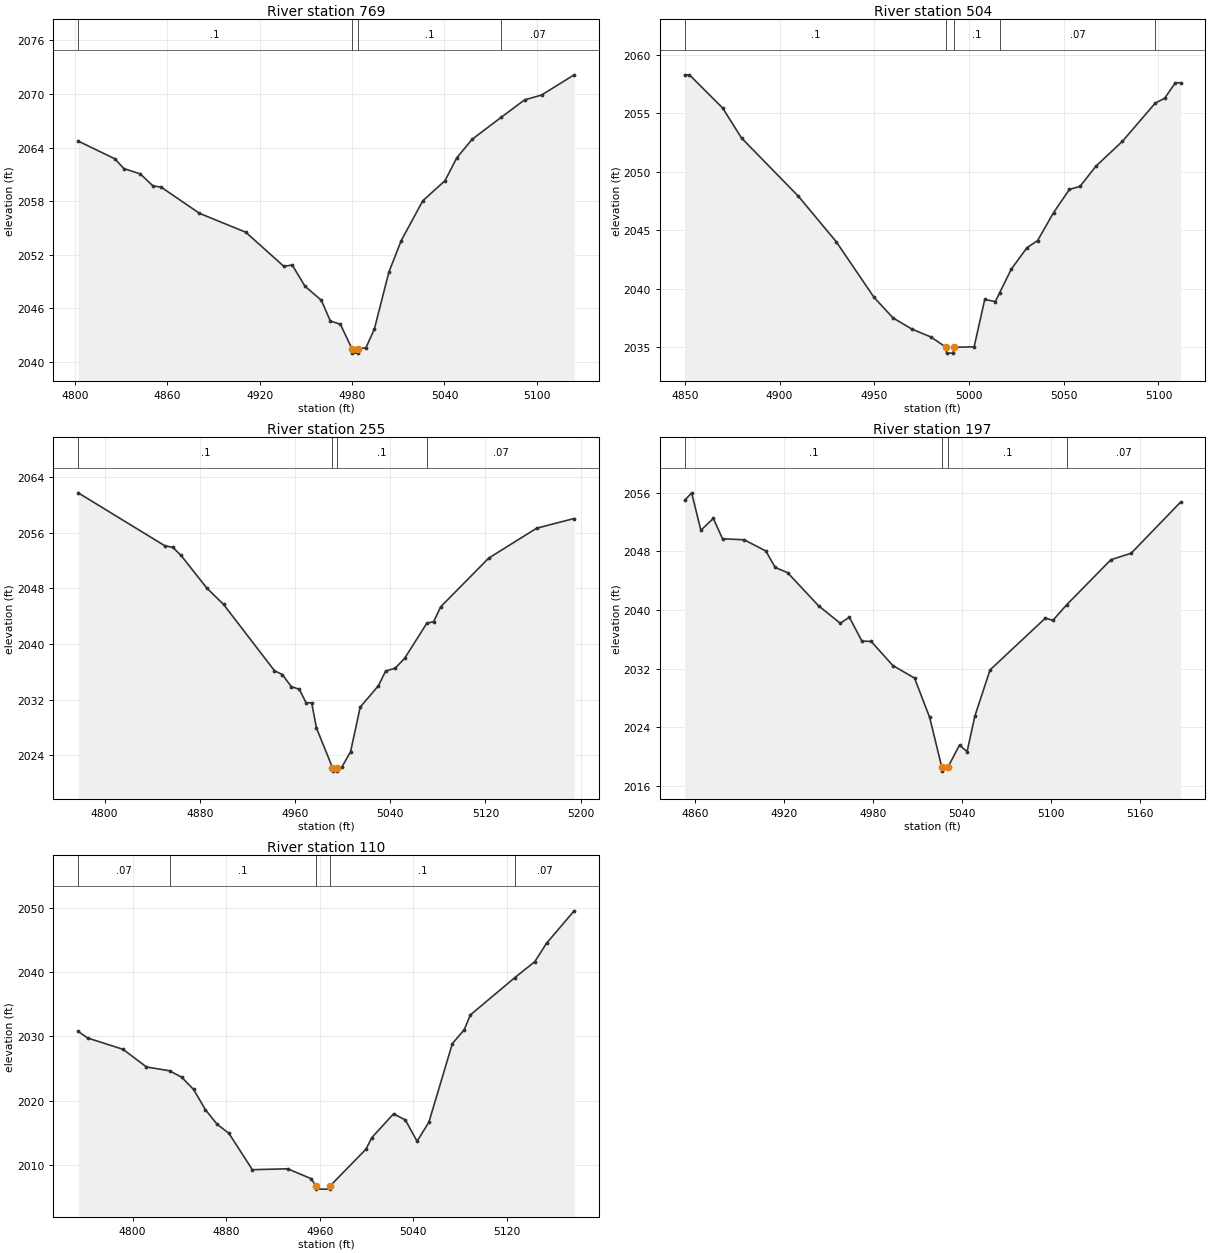
Type RM Length L Ch R = 1,769,265,265,265
BEGIN DESCRIPTION:
Stream0256 2.0
END DESCRIPTION:
XS GIS Cut Line= 3
      1825951.72     13895587.37      1826010.76     13895742.79
      1826075.87     13895884.28
#Sta/Elev= 30
  4802.2 2064.72  4826.0 2062.73  4831.8 2061.64  4842.5 2061.04  4850.7 2059.70
  4856.1 2059.55  4880.9 2056.62  4911.0 2054.50  4935.8 2050.66  4941.1 2050.83
  4949.4 2048.45  4960.1 2046.86  4965.9 2044.54  4972.4 2044.18  4979.9 2041.44
  4980.1 2040.94  4983.6 2040.94  4983.9 2041.44  4989.0 2041.53  4994.5 2043.65
  5003.9 2050.02  5011.9 2053.55  5025.9 2058.02  5040.4 2060.29  5047.9 2062.82
  5057.9 2064.91  5076.7 2067.37  5092.0 2069.34  5103.0 2069.88  5124.2 2072.15
#Mann=4,-1,0
  4802.2     0.1       0  4979.9    0.05       0  4983.9     0.1       0
  5076.7    0.07       0
Bank Sta=4979.9,4983.9
Exp/Cntr=0.3,0.1

Type RM Length L Ch R = 1,504,249,249,249
BEGIN DESCRIPTION:
Stream0256 1.0
END DESCRIPTION:
XS GIS Cut Line= 3
      1825775.00     13895675.00      1825775.00     13895825.00
      1825825.00     13895925.00
#Sta/Elev= 30
  4849.9 2058.30  4852.4 2058.30  4869.9 2055.47  4879.9 2052.90  4909.9 2047.92
  4929.9 2044.03  4949.9 2039.26  4959.9 2037.51  4969.9 2036.55  4979.9 2035.88
  4987.9 2035.00  4988.2 2034.50  4991.7 2034.50  4991.9 2035.00  5002.7 2035.04
  5008.3 2039.09  5013.9 2038.91  5016.1 2039.64  5022.3 2041.68  5030.6 2043.52
  5036.2 2044.12  5044.6 2046.51  5053.0 2048.50  5058.6 2048.76  5067.0 2050.49
  5081.0 2052.62  5098.3 2055.88  5103.3 2056.30  5108.9 2057.62  5111.7 2057.62
#Mann=5,-1,0
  4849.9     0.1       0  4987.9    0.05       0  4991.9     0.1       0
  5016.1    0.07       0  5098.3     0.1       0
Bank Sta=4987.9,4991.9
Exp/Cntr=0.3,0.1

Type RM Length L Ch R = 1,255,58,58,58
BEGIN DESCRIPTION:
Stream0256 0.0
END DESCRIPTION:
XS GIS Cut Line= 4
      1825682.67     13895620.36      1825552.43     13895767.09
      1825515.97     13895826.99      1825535.06     13895976.25
#Sta/Elev= 30
  4777.8 2061.73  4850.7 2054.11  4857.3 2053.90  4864.2 2052.74  4885.8 2048.06
  4900.0 2045.69  4942.7 2036.18  4949.3 2035.62  4956.9 2033.88  4963.6 2033.51
  4969.3 2031.56  4974.0 2031.56  4978.0 2027.96  4991.5 2022.24  4991.8 2021.74
  4995.3 2021.74  4995.5 2022.24  4999.4 2022.33  5006.7 2024.54  5014.8 2030.94
  5030.1 2034.01  5036.2 2036.13  5044.1 2036.52  5052.2 2037.96  5070.7 2042.97
  5076.6 2043.23  5082.4 2045.35  5122.8 2052.35  5163.1 2056.65  5194.6 2058.04
#Mann=4,-1,0
  4777.8     0.1       0  4991.5    0.05       0  4995.5     0.1       0
  5070.7    0.07       0
Bank Sta=4991.5,4995.5
Exp/Cntr=0.3,0.1

Type RM Length L Ch R = 1,197,87,87,87
BEGIN DESCRIPTION:
Stream0256 0.1
END DESCRIPTION:
XS GIS Cut Line= 3
      1825584.65     13895628.79      1825498.20     13895745.39
      1825463.65     13895931.25
#Sta/Elev= 30
  4853.0 2054.94  4857.7 2055.96  4863.9 2050.85  4872.3 2052.47  4878.5 2049.70
  4893.1 2049.56  4907.7 2048.03  4914.0 2045.79  4922.4 2045.07  4943.2 2040.57
  4957.8 2038.19  4964.0 2039.00  4972.4 2035.76  4978.7 2035.70  4993.3 2032.42
  5007.9 2030.71  5018.1 2025.34  5026.3 2018.53  5026.5 2018.03  5030.3 2018.53
  5038.2 2021.58  5043.3 2020.69  5048.6 2025.57  5058.8 2031.83  5096.1 2038.89
  5101.1 2038.57  5110.5 2040.72  5140.2 2046.84  5153.9 2047.73  5187.2 2054.70
#Mann=4,-1,0
  4853.0     0.1       0  5026.3    0.05       0  5030.3     0.1       0
  5110.5    0.07       0
Bank Sta=5026.3,5030.3
Exp/Cntr=0.3,0.1

Type RM Length L Ch R = 1,110,0,0,0
BEGIN DESCRIPTION:
Stream0256 T
END DESCRIPTION:
XS GIS Cut Line= 2
      1825391.90     13895486.93      1825440.04     13895908.49
#Sta/Elev= 30
  4753.4 2030.79  4761.5 2029.76  4791.7 2028.00  4811.8 2025.25  4831.5 2024.65
  4842.0 2023.64  4852.1 2021.74  4862.2 2018.59  4872.2 2016.32  4882.3 2014.91
  4902.4 2009.23  4932.6 2009.37  4952.8 2007.82  4956.7 2006.70  4957.2 2006.20
  4968.4 2006.20  4968.9 2006.70  4999.6 2012.43  5004.6 2014.23  5023.2 2017.94
  5033.3 2016.98  5043.3 2013.66  5053.4 2016.63  5073.5 2028.89  5083.6 2031.04
  5088.9 2033.36  5126.9 2039.17  5144.0 2041.66  5154.1 2044.54  5177.7 2049.59
#Mann=5,-1,0
  4753.4    0.07       0  4831.5     0.1       0  4956.7    0.05       0
  4968.9     0.1       0  5126.9    0.07       0
Bank Sta=4956.7,4968.9
Exp/Cntr=0.3,0.1

Chan Stop Cuts=-1