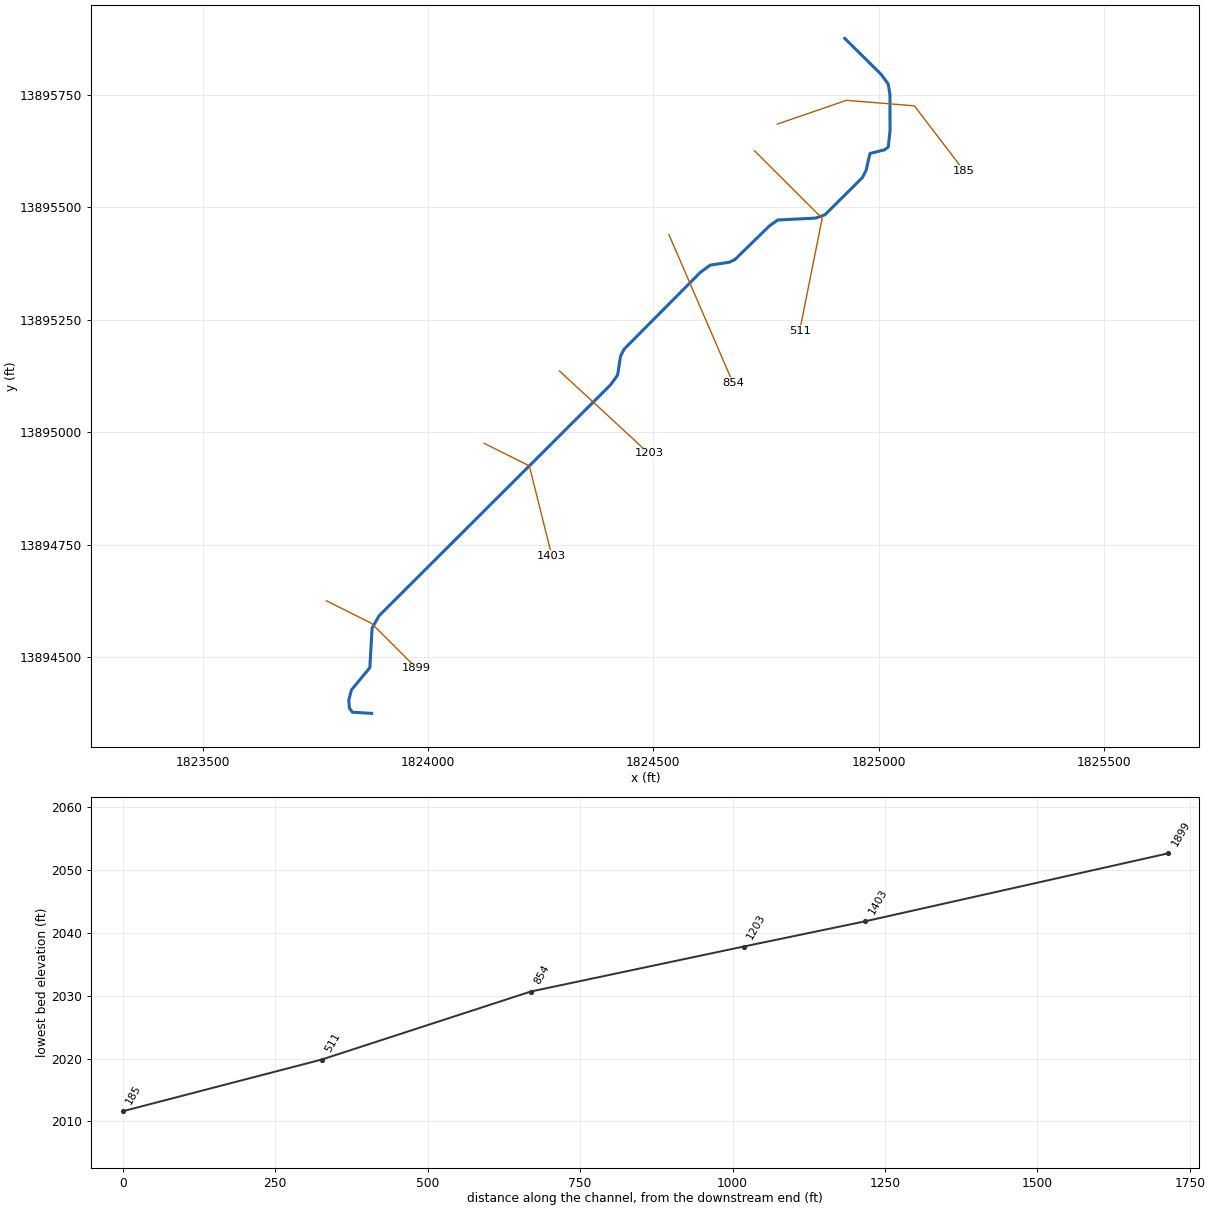
--- Stream0257.prj (project) ---

Proj Title=Stream0257 Base Level Engineering
Current Plan=p01
Default Exp/Contr=0.3,0.1
English Units
Geom File=g01
Flow File=f01
Plan File=p01
BEGIN DESCRIPTION:
Stream0257
END DESCRIPTION:

--- Stream0257.p01 (plan) ---

Plan Title=Multiple Run
Short Identifier=Multiple
Geom File=g01
Flow File=f01
Subcritical Flow
K Sum by GR= 0
Std Step Tol= 0.01
Critical Tol= 0.01
Num of Std Step Trials= 20
Max Error Tol= 0.3
Flow Tol Ratio= 0.001
Split Flow NTrial= 30
Split Flow Tol= 0.02
Split Flow Ratio= 0.02
Log Output Level= 0
Friction Slope Method= 1
Unsteady Friction Slope Method= 2
Unsteady Bridges Friction Slope Method= 1
Parabolic Critical Depth
Global Vel Dist=  1 , 1 , 1
Global Log Level= 0
CheckData=True
Encroach Param= -1, 0, 0, 0
BEGIN DESCRIPTION:
Multiple Run
END DESCRIPTION:

--- Stream0257.f01 (steady flow) ---

Flow Title=Multiple
Number of Profiles=7
Profile Names=10-year,25-year,50-year,1pct_min,100-year,1pct_plu,500-year
River Rch & RM= Stream0257,Reach-1,1899
     459     748    1013     667    1331    2655    2259
Boundary for River Rch & Prof#=Stream0257,Reach-1,1
Up Type=0
Dn Type=3
Dn Slope=0.005
Boundary for River Rch & Prof#=Stream0257,Reach-1,2
Up Type=0
Dn Type=3
Dn Slope=0.005
Boundary for River Rch & Prof#=Stream0257,Reach-1,3
Up Type=0
Dn Type=3
Dn Slope=0.005
Boundary for River Rch & Prof#=Stream0257,Reach-1,4
Up Type=0
Dn Type=3
Dn Slope=0.005
Boundary for River Rch & Prof#=Stream0257,Reach-1,5
Up Type=0
Dn Type=3
Dn Slope=0.005
Boundary for River Rch & Prof#=Stream0257,Reach-1,6
Up Type=0
Dn Type=3
Dn Slope=0.005
Boundary for River Rch & Prof#=Stream0257,Reach-1,7
Up Type=0
Dn Type=3
Dn Slope=0.005

--- Stream0257.g01 (geometry) ---

Geom Title=Existing Conditions

River Reach=Stream0257,Reach-1
Reach XY= 30
      1823875.00     13894375.00      1823832.24     13894377.61
      1823825.71     13894386.73      1823824.46     13894404.72
      1823830.31     13894427.00      1823871.14     13894476.55
      1823876.16     13894564.52      1823891.46     13894591.75
      1824405.21     13895104.91      1824421.02     13895126.65
      1824427.53     13895168.95      1824435.78     13895184.68
      1824604.91     13895355.21      1824626.65     13895371.03
      1824668.95     13895377.54      1824681.04     13895383.18
      1824758.26     13895458.51      1824776.50     13895471.37
      1824859.79     13895475.52      1824881.19     13895482.86
      1824964.16     13895565.54      1824972.41     13895581.38
      1824981.06     13895619.19      1825012.93     13895627.14
      1825021.61     13895633.44      1825025.61     13895669.48
      1825025.33     13895750.09      1825021.53     13895773.55
      1825005.51     13895795.21      1824925.00     13895875.00

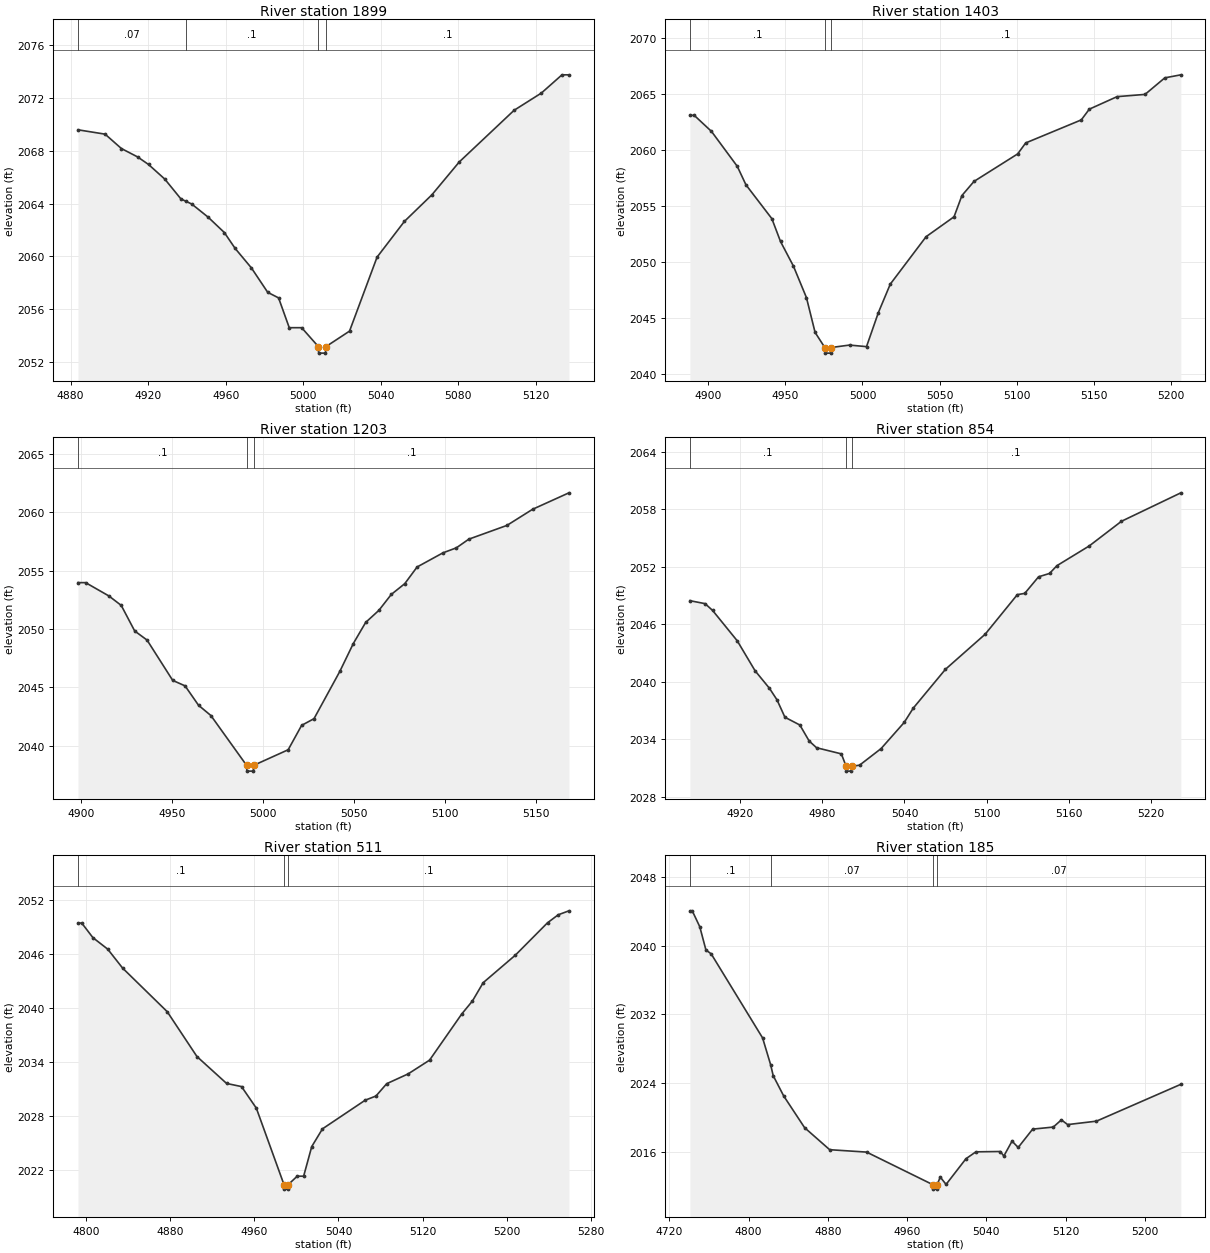
Type RM Length L Ch R = 1,1899,496,496,496
BEGIN DESCRIPTION:
Stream0257 3.0
END DESCRIPTION:
XS GIS Cut Line= 3
      1823774.97     13894625.02      1823875.00     13894575.00
      1823975.03     13894474.97
#Sta/Elev= 30
  4883.8 2069.60  4897.8 2069.27  4906.2 2068.18  4914.6 2067.54  4920.2 2066.97
  4928.6 2065.86  4936.9 2064.36  4939.6 2064.17  4942.5 2063.97  4950.9 2062.98
  4959.3 2061.81  4964.9 2060.60  4973.3 2059.12  4981.7 2057.27  4987.3 2056.85
  4992.8 2054.59  4999.2 2054.59  5007.8 2053.16  5008.0 2052.66  5011.5 2052.66
  5011.8 2053.16  5023.9 2054.33  5038.1 2059.94  5052.2 2062.65  5066.4 2064.67
  5080.5 2067.16  5108.8 2071.08  5122.9 2072.39  5133.5 2073.77  5137.1 2073.77
#Mann=4,-1,0
  4883.8    0.07       0  4939.6     0.1       0  5007.8    0.05       0
  5011.8     0.1       0
Bank Sta=5007.8,5011.8
Exp/Cntr=0.3,0.1

Type RM Length L Ch R = 1,1403,200,200,200
BEGIN DESCRIPTION:
Stream0257 2.0
END DESCRIPTION:
XS GIS Cut Line= 3
      1824125.01     13894975.00      1824225.00     13894925.00
      1824275.01     13894724.95
#Sta/Elev= 30
  4888.2 2063.12  4891.0 2063.12  4902.2 2061.68  4918.9 2058.56  4924.5 2056.91
  4941.3 2053.88  4946.9 2051.84  4955.3 2049.63  4963.7 2046.82  4969.3 2043.71
  4975.6 2042.36  4975.9 2041.86  4979.4 2041.86  4979.6 2042.36  4991.6 2042.58
  5002.6 2042.44  5010.3 2045.49  5018.0 2048.03  5041.2 2052.27  5059.3 2054.05
  5064.4 2055.95  5072.2 2057.21  5100.5 2059.67  5105.7 2060.65  5141.7 2062.71
  5146.9 2063.67  5164.9 2064.79  5183.0 2064.99  5195.8 2066.47  5206.2 2066.74
#Mann=3,-1,0
  4888.2     0.1       0  4975.6    0.05       0  4979.6     0.1       0
Bank Sta=4975.6,4979.6
Exp/Cntr=0.3,0.1

Type RM Length L Ch R = 1,1203,349,349,349
BEGIN DESCRIPTION:
Mapping XS c5cf4677
END DESCRIPTION:
XS GIS Cut Line= 2
      1824292.12     13895135.77      1824490.38     13894952.48
#Sta/Elev= 30
  4898.2 2053.97  4902.4 2053.97  4915.2 2052.83  4922.0 2052.02  4929.4 2049.83
  4936.2 2049.05  4950.3 2045.60  4957.1 2045.13  4964.5 2043.47  4971.3 2042.59
  4990.9 2038.33  4991.1 2037.83  4994.6 2037.83  4994.9 2038.33  5013.8 2039.66
  5021.2 2041.75  5028.0 2042.32  5042.2 2046.37  5049.6 2048.75  5056.4 2050.56
  5063.7 2051.60  5070.5 2052.96  5077.9 2053.88  5084.7 2055.31  5098.9 2056.52
  5106.3 2056.95  5113.1 2057.69  5134.1 2058.87  5148.2 2060.25  5168.2 2061.66
#Mann=3,-1,0
  4898.2     0.1       0  4990.9    0.05       0  4994.9     0.1       0
Bank Sta=4990.9,4994.9
Exp/Cntr=0.3,0.1

Type RM Length L Ch R = 1,854,343,343,343
BEGIN DESCRIPTION:
Mapping XS 0a8c5b7b
END DESCRIPTION:
XS GIS Cut Line= 2
      1824534.97     13895438.74      1824676.96     13895109.56
#Sta/Elev= 30
  4883.3 2048.45  4894.4 2048.14  4899.9 2047.43  4917.9 2044.26  4930.9 2041.14
  4941.4 2039.31  4946.9 2038.11  4952.7 2036.29  4963.6 2035.48  4970.4 2033.81
  4975.8 2033.11  4993.9 2032.47  4997.4 2031.17  4997.6 2030.67  5001.1 2030.67
  5001.4 2031.17  5007.2 2031.29  5022.9 2033.02  5039.8 2035.75  5046.4 2037.24
  5069.9 2041.29  5098.9 2044.95  5122.4 2049.08  5127.8 2049.21  5137.9 2050.94
  5145.9 2051.29  5151.3 2052.10  5174.9 2054.16  5198.4 2056.73  5241.8 2059.70
#Mann=3,-1,0
  4883.3     0.1       0  4997.4    0.05       0  5001.4     0.1       0
Bank Sta=4997.4,5001.4
Exp/Cntr=0.3,0.1

Type RM Length L Ch R = 1,511,326,326,326
BEGIN DESCRIPTION:
Stream0257 1.0
END DESCRIPTION:
XS GIS Cut Line= 3
      1824724.98     13895625.02      1824875.00     13895475.00
      1824825.00     13895225.01
#Sta/Elev= 30
  4792.2 2049.42  4795.8 2049.42  4806.4 2047.80  4820.5 2046.52  4834.7 2044.41
  4877.1 2039.57  4905.4 2034.58  4933.6 2031.59  4947.8 2031.24  4961.9 2028.84
  4988.2 2020.34  4988.5 2019.84  4992.0 2019.84  4992.2 2020.34  5000.8 2021.28
  5006.9 2021.28  5014.6 2024.57  5024.8 2026.54  5065.5 2029.73  5075.7 2030.19
  5085.9 2031.56  5106.3 2032.65  5126.7 2034.18  5157.3 2039.31  5167.5 2040.76
  5177.7 2042.79  5208.3 2045.85  5238.9 2049.45  5249.1 2050.34  5259.3 2050.78
#Mann=3,-1,0
  4792.2     0.1       0  4988.2    0.05       0  4992.2     0.1       0
Bank Sta=4988.2,4992.2
Exp/Cntr=0.3,0.1

Type RM Length L Ch R = 1,185,0,0,0
BEGIN DESCRIPTION:
Stream0257 0.0
END DESCRIPTION:
XS GIS Cut Line= 4
      1824775.52     13895684.41      1824928.72     13895737.23
      1825079.61     13895725.02      1825190.07     13895580.17
#Sta/Elev= 30
  4740.8 2044.09  4743.2 2044.09  4750.8 2042.23  4757.0 2039.52  4762.3 2039.07
  4814.2 2029.26  4822.3 2026.14  4824.9 2024.86  4835.5 2022.49  4856.6 2018.79
  4881.9 2016.22  4919.2 2015.94  4986.4 2012.12  4986.7 2011.62  4990.2 2011.62
  4990.4 2012.12  4993.5 2013.03  4999.4 2012.17  5019.5 2015.17  5029.5 2015.97
  5054.2 2016.01  5057.7 2015.48  5066.0 2017.22  5072.2 2016.48  5086.8 2018.62
  5107.6 2018.86  5115.8 2019.70  5122.1 2019.15  5151.2 2019.55  5236.4 2023.85
#Mann=4,-1,0
  4740.8     0.1       0  4822.3    0.07       0  4986.4    0.05       0
  4990.4    0.07       0
Bank Sta=4986.4,4990.4
Exp/Cntr=0.3,0.1

Chan Stop Cuts=-1