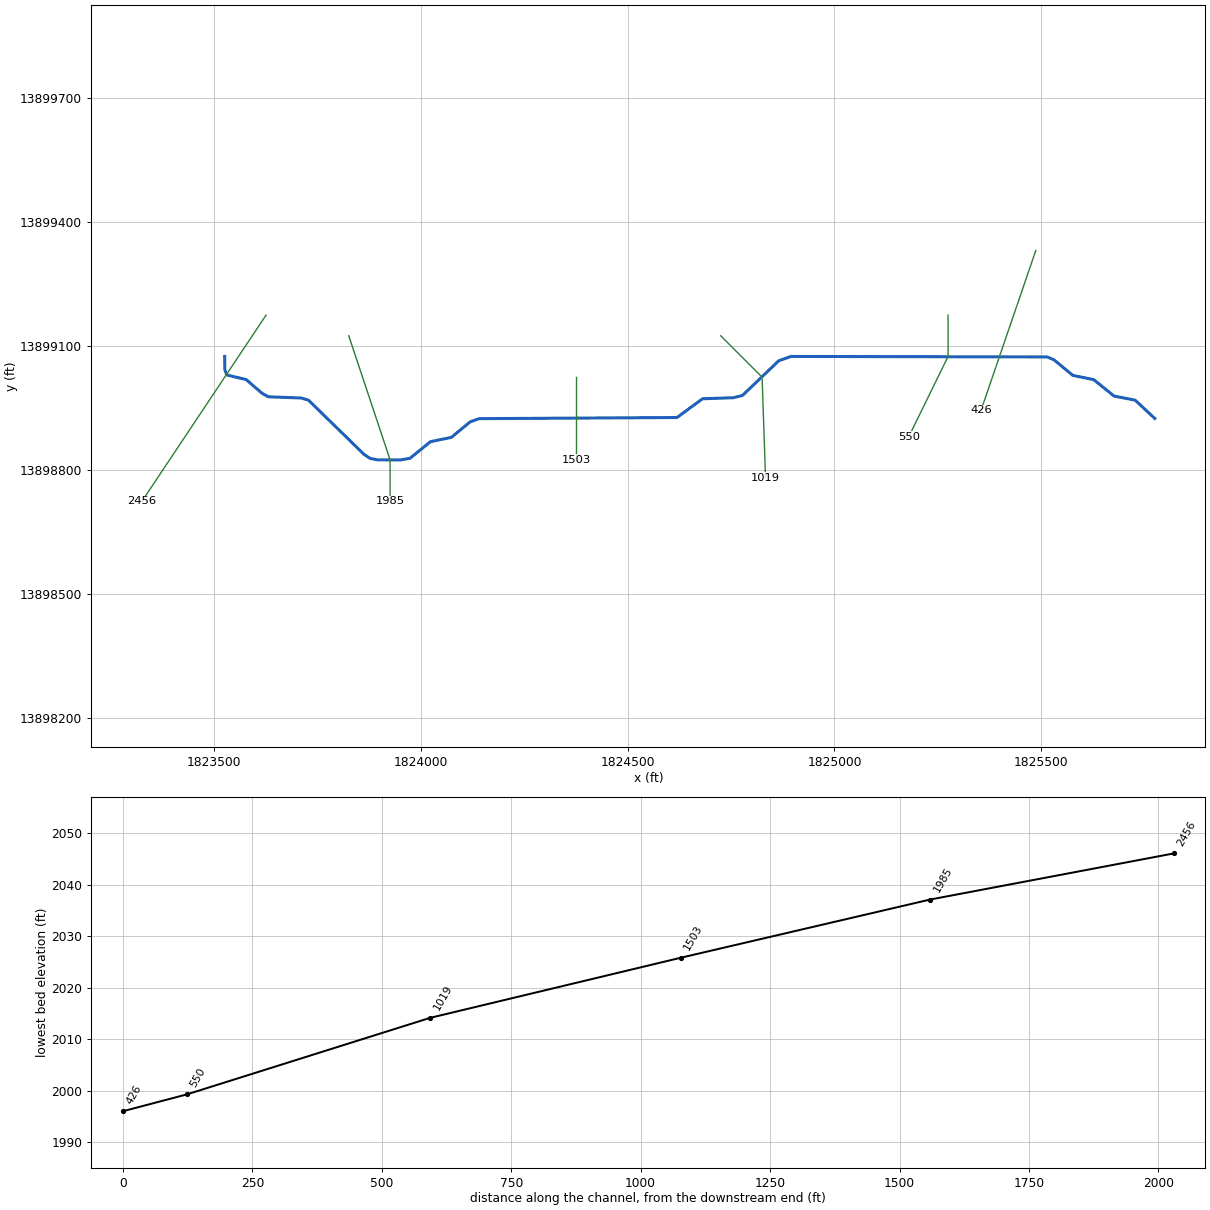
--- Stream0258.prj (project) ---

Proj Title=Stream0258 Base Level Engineering
Current Plan=p01
Default Exp/Contr=0.3,0.1
English Units
Geom File=g01
Flow File=f01
Plan File=p01
BEGIN DESCRIPTION:
Stream0258
END DESCRIPTION:

--- Stream0258.p01 (plan) ---

Plan Title=Multiple Run
Short Identifier=Multiple
Geom File=g01
Flow File=f01
Subcritical Flow
K Sum by GR= 0
Std Step Tol= 0.01
Critical Tol= 0.01
Num of Std Step Trials= 20
Max Error Tol= 0.3
Flow Tol Ratio= 0.001
Split Flow NTrial= 30
Split Flow Tol= 0.02
Split Flow Ratio= 0.02
Log Output Level= 0
Friction Slope Method= 1
Unsteady Friction Slope Method= 2
Unsteady Bridges Friction Slope Method= 1
Parabolic Critical Depth
Global Vel Dist=  1 , 1 , 1
Global Log Level= 0
CheckData=True
Encroach Param= -1, 0, 0, 0
BEGIN DESCRIPTION:
Multiple Run
END DESCRIPTION:

--- Stream0258.f01 (steady flow) ---

Flow Title=Multiple
Number of Profiles=7
Profile Names=10-year,25-year,50-year,1pct_min,100-year,1pct_plu,500-year
River Rch & RM= Stream0258,Reach-1,2456
     682    1148    1587    1063    2121    4233    3744
Boundary for River Rch & Prof#=Stream0258,Reach-1,1
Up Type=0
Dn Type=3
Dn Slope=0.005
Boundary for River Rch & Prof#=Stream0258,Reach-1,2
Up Type=0
Dn Type=3
Dn Slope=0.005
Boundary for River Rch & Prof#=Stream0258,Reach-1,3
Up Type=0
Dn Type=3
Dn Slope=0.005
Boundary for River Rch & Prof#=Stream0258,Reach-1,4
Up Type=0
Dn Type=3
Dn Slope=0.005
Boundary for River Rch & Prof#=Stream0258,Reach-1,5
Up Type=0
Dn Type=3
Dn Slope=0.005
Boundary for River Rch & Prof#=Stream0258,Reach-1,6
Up Type=0
Dn Type=3
Dn Slope=0.005
Boundary for River Rch & Prof#=Stream0258,Reach-1,7
Up Type=0
Dn Type=3
Dn Slope=0.005

--- Stream0258.g01 (geometry) ---

Geom Title=Existing Conditions

River Reach=Stream0258,Reach-1
Reach XY= 30
      1823525.00     13899075.00      1823525.06     13899043.44
      1823529.90     13899030.28      1823577.00     13899018.96
      1823615.29     13898985.79      1823630.94     13898977.31
      1823709.78     13898974.48      1823727.43     13898969.48
      1823861.70     13898838.34      1823876.50     13898828.46
      1823895.05     13898824.79      1823950.00     13898824.58
      1823973.41     13898828.67      1824022.82     13898868.88
      1824073.26     13898879.19      1824118.92     13898916.91
      1824140.21     13898924.49      1824619.06     13898927.26
      1824680.98     13898972.64      1824754.95     13898975.13
      1824777.42     13898980.54      1824865.21     13899064.50
      1824894.98     13899075.04      1825514.50     13899073.80
      1825531.08     13899066.91      1825576.74     13899029.19
      1825627.20     13899018.93      1825676.67     13898979.04
      1825727.36     13898969.33      1825775.00     13898925.00

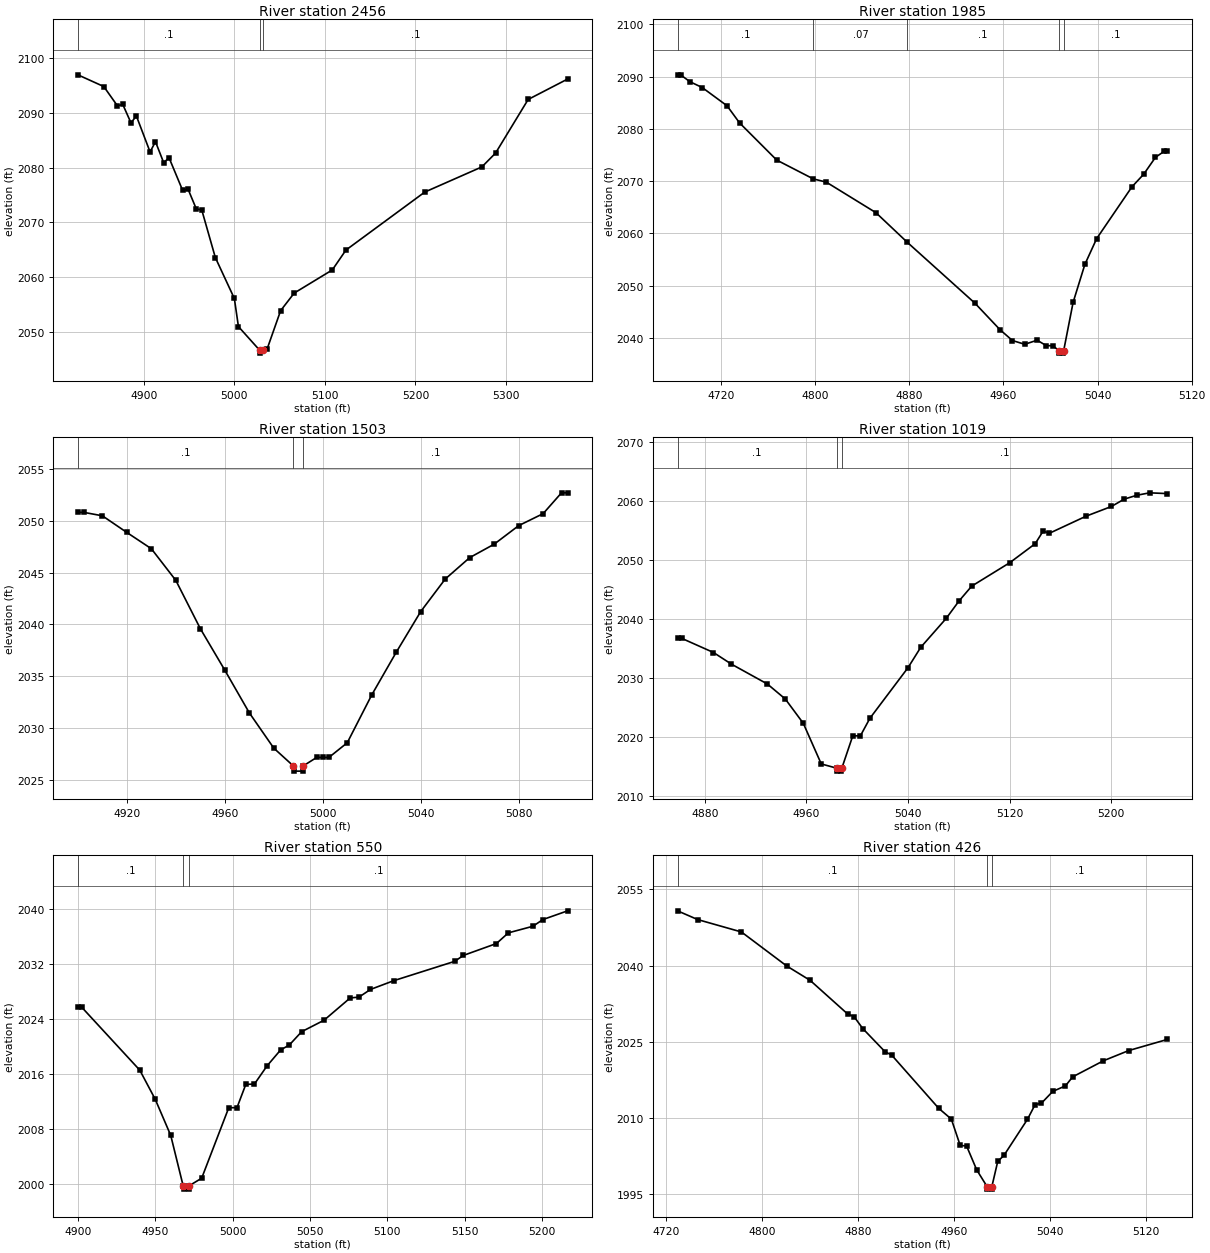
Type RM Length L Ch R = 1,2456,471,471,471
BEGIN DESCRIPTION:
Stream0258 5.0
END DESCRIPTION:
XS GIS Cut Line= 3
      1823625.03     13899175.04      1823525.00     13899025.00
      1823324.99     13898724.99
#Sta/Elev= 30
  4827.2 2096.95  4855.8 2094.81  4870.8 2091.30  4876.8 2091.53  4885.8 2088.18
  4891.8 2089.43  4906.9 2082.87  4912.9 2084.73  4921.9 2080.92  4927.9 2081.79
  4942.9 2075.83  4948.9 2076.05  4958.0 2072.44  4964.0 2072.27  4979.0 2063.57
  5000.0 2056.09  5004.5 2050.96  5028.1 2046.61  5028.3 2046.11  5032.1 2046.61
  5036.1 2046.82  5051.1 2053.87  5066.1 2057.08  5108.2 2061.31  5123.2 2064.93
  5210.3 2075.53  5273.4 2080.13  5288.5 2082.65  5324.5 2092.45  5368.1 2096.18
#Mann=3,-1,0
  4827.2     0.1       0  5028.1    0.05       0  5032.1     0.1       0
Bank Sta=5028.1,5032.1
Exp/Cntr=0.3,0.1

Type RM Length L Ch R = 1,1985,482,482,482
BEGIN DESCRIPTION:
Stream0258 4.0
END DESCRIPTION:
XS GIS Cut Line= 3
      1823825.01     13899124.96      1823925.00     13898825.00
      1823925.00     13898724.98
#Sta/Elev= 30
  4683.0 2090.32  4685.6 2090.32  4693.5 2089.01  4704.0 2087.89  4725.1 2084.40
  4735.7 2081.14  4767.3 2074.03  4798.4 2070.43  4809.4 2069.82  4851.6 2063.98
  4878.4 2058.29  4935.9 2046.65  4957.0 2041.63  4967.6 2039.55  4978.1 2038.83
  4988.6 2039.61  4996.5 2038.56  5001.7 2038.56  5007.2 2037.64  5007.4 2037.14
  5010.9 2037.14  5011.2 2037.64  5019.2 2046.85  5029.2 2054.10  5039.2 2059.02
  5069.2 2068.92  5079.2 2071.33  5089.2 2074.56  5096.7 2075.72  5099.2 2075.72
#Mann=5,-1,0
  4683.0     0.1       0  4798.4    0.07       0  4878.4     0.1       0
  5007.2    0.05       0  5011.2     0.1       0
Bank Sta=5007.2,5011.2
Exp/Cntr=0.3,0.1

Type RM Length L Ch R = 1,1503,484,484,484
BEGIN DESCRIPTION:
Stream0258 3.0
END DESCRIPTION:
XS GIS Cut Line= 3
      1824375.00     13899025.01      1824375.00     13898925.00
      1824375.00     13898825.01
#Sta/Elev= 28
  4900.0 2050.81  4902.5 2050.81  4910.0 2050.48  4920.0 2048.87  4930.0 2047.30
  4940.0 2044.24  4950.0 2039.58  4960.0 2035.57  4970.0 2031.45  4980.0 2028.04
  4988.0 2026.32  4988.3 2025.82  4991.8 2025.82  4992.0 2026.32  4997.5 2027.14
  5000.0 2027.14  5002.5 2027.14  5010.0 2028.56  5020.0 2033.18  5030.0 2037.30
  5040.0 2041.23  5050.0 2044.37  5060.0 2046.44  5070.0 2047.74  5080.0 2049.53
  5090.0 2050.69  5097.5 2052.70  5100.0 2052.70
#Mann=3,-1,0
  4900.0     0.1       0  4988.0    0.05       0  4992.0     0.1       0
Bank Sta=4988,4992
Exp/Cntr=0.3,0.1

Type RM Length L Ch R = 1,1019,469,469,469
BEGIN DESCRIPTION:
Stream0258 2.0
END DESCRIPTION:
XS GIS Cut Line= 3
      1824725.01     13899124.99      1824825.00     13899025.00
      1824833.27     13898781.15
#Sta/Elev= 30
  4858.6 2036.63  4862.1 2036.63  4886.9 2034.25  4901.0 2032.28  4929.3 2028.91
  4943.4 2026.37  4957.6 2022.24  4971.7 2015.36  4983.9 2014.64  4984.1 2014.14
  4987.6 2014.14  4987.9 2014.64  4996.5 2020.12  5002.5 2020.12  5010.0 2023.10
  5040.0 2031.68  5050.0 2035.13  5070.1 2040.05  5080.1 2042.98  5090.1 2045.50
  5120.1 2049.48  5140.1 2052.70  5146.3 2054.83  5151.3 2054.47  5180.1 2057.36
  5200.1 2059.01  5210.1 2060.25  5220.1 2060.91  5230.1 2061.32  5244.0 2061.19
#Mann=3,-1,0
  4858.6     0.1       0  4983.9    0.05       0  4987.9     0.1       0
Bank Sta=4983.9,4987.9
Exp/Cntr=0.3,0.1

Type RM Length L Ch R = 1,550,124,124,124
BEGIN DESCRIPTION:
Stream0258 1.0
END DESCRIPTION:
XS GIS Cut Line= 3
      1825275.00     13899175.02      1825275.00     13899075.00
      1825179.77     13898880.59
#Sta/Elev= 30
  4900.0 2025.71  4902.5 2025.71  4940.0 2016.57  4950.0 2012.33  4960.0 2007.09
  4968.0 1999.79  4968.3 1999.29  4971.8 1999.29  4972.0 1999.79  4980.0 2000.88
  4997.5 2011.12  5002.8 2011.12  5008.5 2014.50  5014.1 2014.56  5022.3 2017.21
  5031.0 2019.51  5036.6 2020.22  5044.6 2022.16  5059.1 2023.83  5076.0 2027.07
  5081.6 2027.18  5089.1 2028.30  5104.1 2029.57  5143.5 2032.38  5149.1 2033.24
  5170.5 2034.97  5178.2 2036.52  5194.1 2037.48  5200.5 2038.45  5216.5 2039.72
#Mann=3,-1,0
  4900.0     0.1       0  4968.0    0.05       0  4972.0     0.1       0
Bank Sta=4968,4972
Exp/Cntr=0.3,0.1

Type RM Length L Ch R = 1,426,0,0,0
BEGIN DESCRIPTION:
Stream0258 0.0
END DESCRIPTION:
XS GIS Cut Line= 2
      1825487.06     13899331.12      1825354.69     13898944.66
#Sta/Elev= 30
  4729.3 2050.76  4746.1 2049.04  4782.6 2046.60  4820.3 2039.92  4839.9 2037.08
  4871.2 2030.46  4876.5 2029.95  4883.8 2027.60  4902.5 2023.01  4907.8 2022.41
  4947.2 2011.89  4957.7 2009.78  4965.1 2004.59  4970.4 2004.50  4978.9 1999.77
  4987.5 1996.50  4987.7 1996.00  4991.2 1996.00  4991.5 1996.50  4996.4 2001.45
  5001.6 2002.64  5021.2 2009.74  5027.6 2012.64  5032.9 2012.92  5042.3 2015.23
  5052.9 2016.32  5058.9 2018.09  5084.6 2021.26  5105.7 2023.27  5137.8 2025.45
#Mann=3,-1,0
  4729.3     0.1       0  4987.5    0.05       0  4991.5     0.1       0
Bank Sta=4987.5,4991.5
Exp/Cntr=0.3,0.1

Chan Stop Cuts=-1