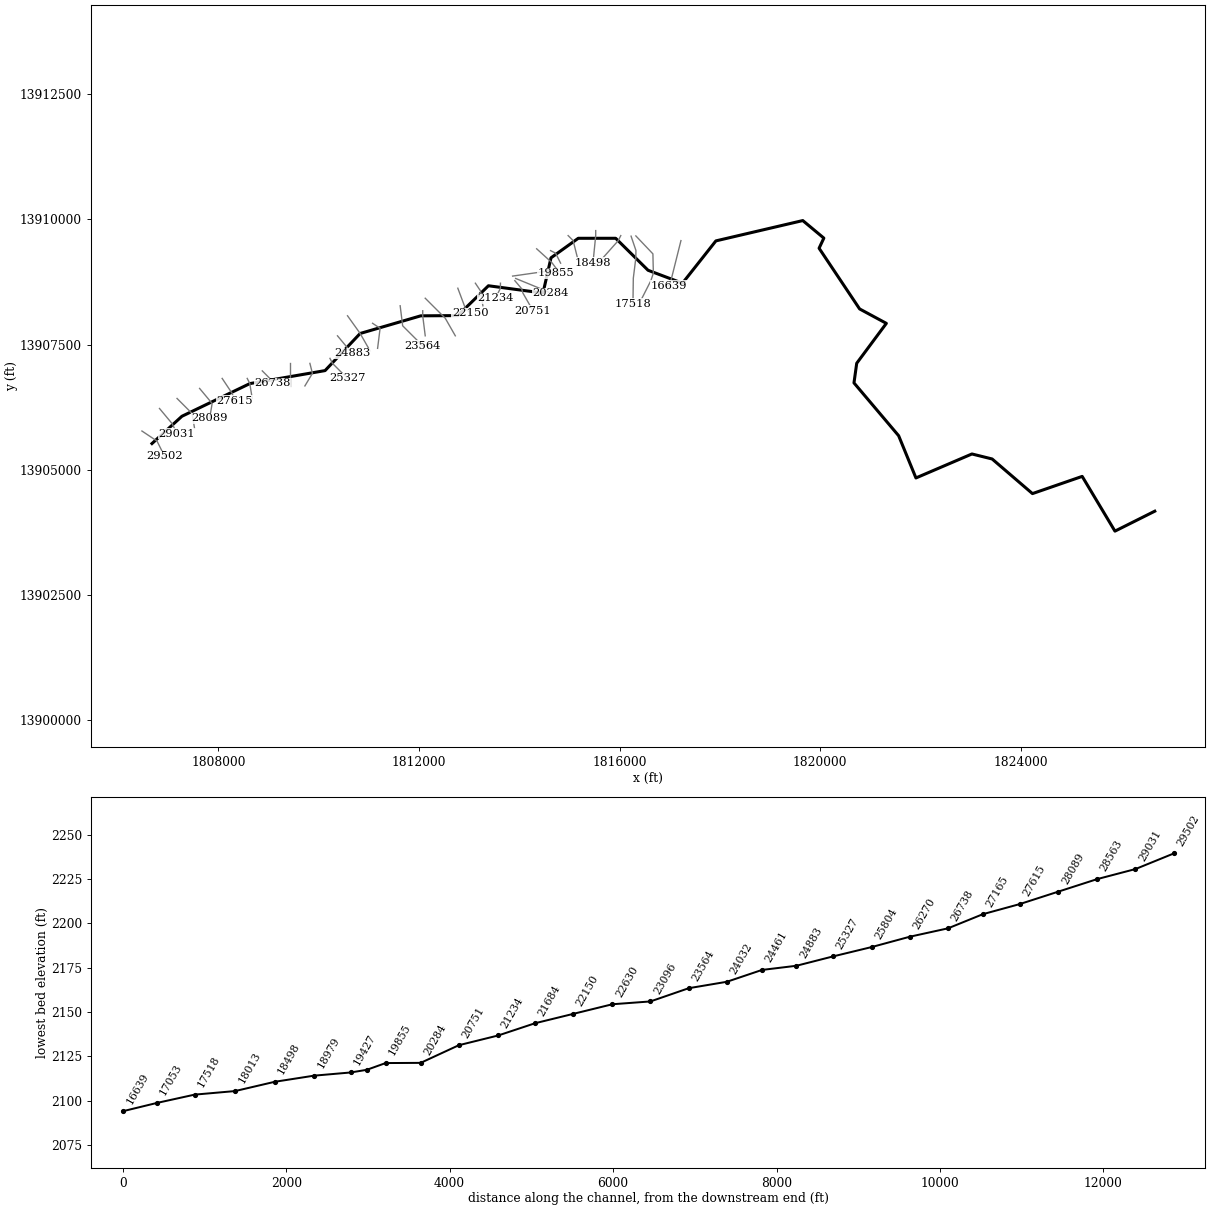
--- Stream0262.prj (project) ---

Proj Title=Stream0262 Base Level Engineering
Current Plan=p01
Default Exp/Contr=0.3,0.1
English Units
Geom File=g01
Flow File=f01
Plan File=p01
BEGIN DESCRIPTION:
Stream0262
END DESCRIPTION:

--- Stream0262.p01 (plan) ---

Plan Title=Multiple Run
Short Identifier=Multiple
Geom File=g01
Flow File=f01
Subcritical Flow
K Sum by GR= 0
Std Step Tol= 0.01
Critical Tol= 0.01
Num of Std Step Trials= 20
Max Error Tol= 0.3
Flow Tol Ratio= 0.001
Split Flow NTrial= 30
Split Flow Tol= 0.02
Split Flow Ratio= 0.02
Log Output Level= 0
Friction Slope Method= 1
Unsteady Friction Slope Method= 2
Unsteady Bridges Friction Slope Method= 1
Parabolic Critical Depth
Global Vel Dist=  1 , 1 , 1
Global Log Level= 0
CheckData=True
Encroach Param= -1, 0, 0, 0
BEGIN DESCRIPTION:
Multiple Run
END DESCRIPTION:

--- Stream0262.f01 (steady flow) ---

Flow Title=Multiple
Number of Profiles=7
Profile Names=10-year,25-year,50-year,1pct_min,100-year,1pct_plu,500-year
River Rch & RM= Stream0262,Reach-1,29502
     487     792    1070     700    1397    2787    2350
River Rch & RM= Stream0262,Reach-1,26738
    1055    1804    2517    1697    3385    6754    6056
River Rch & RM= Stream0262,Reach-1,24461
    1322    2287    3213    2179    4347    8674    7877
River Rch & RM= Stream0262,Reach-1,19625
    1797    3154    4475    3061    6107   12186   11264
River Rch & RM= Stream0262,Reach-1,15964
    1984    3495    4973    3408    6800   13568   12595
River Rch & RM= Stream0262,Reach-1,13409
    2667    4772    6860    4747    9472   18899   17887
River Rch & RM= Stream0262,Reach-1,9875
    2847    5106    7351    5093   10162   20276   19238
River Rch & RM= Stream0262,Reach-1,6727
    3934    7156   10403    7270   14506   28943   27948
River Rch & RM= Stream0262,Reach-1,1909
    4112    7487   10888    7612   15187   30302   29276
Boundary for River Rch & Prof#=Stream0262,Reach-1,1
Up Type=0
Dn Type=3
Dn Slope=0.005
Boundary for River Rch & Prof#=Stream0262,Reach-1,2
Up Type=0
Dn Type=3
Dn Slope=0.005
Boundary for River Rch & Prof#=Stream0262,Reach-1,3
Up Type=0
Dn Type=3
Dn Slope=0.005
Boundary for River Rch & Prof#=Stream0262,Reach-1,4
Up Type=0
Dn Type=3
Dn Slope=0.005
Boundary for River Rch & Prof#=Stream0262,Reach-1,5
Up Type=0
Dn Type=3
Dn Slope=0.005
Boundary for River Rch & Prof#=Stream0262,Reach-1,6
Up Type=0
Dn Type=3
Dn Slope=0.005
Boundary for River Rch & Prof#=Stream0262,Reach-1,7
Up Type=0
Dn Type=3
Dn Slope=0.005

--- Stream0262.g01 (geometry) ---

Geom Title=Existing Conditions

River Reach=Stream0262,Reach-1
Reach XY= 30
      1806675.00     13905525.00      1807272.58     13906069.46
      1808626.56     13906721.24      1810127.30     13906980.83
      1810826.50     13907721.39      1812035.50     13908073.80
      1812773.53     13908078.54      1813385.54     13908673.92
      1814473.75     13908528.45      1814633.05     13909231.09
      1815176.58     13909621.17      1815923.50     13909621.39
      1816568.95     13908983.14      1817254.95     13908724.79
      1817922.03     13909569.48      1819654.97     13909974.94
      1820075.00     13909625.00      1819980.08     13909422.72
      1820788.46     13908211.37      1821321.54     13907923.50
      1820730.54     13907127.42      1820675.96     13906735.40
      1821566.86     13905681.06      1821911.68     13904838.37
      1823028.34     13905316.98      1823431.21     13905217.19
      1824235.50     13904526.20      1825227.43     13904869.60
      1825880.71     13903776.89      1826675.00     13904175.00

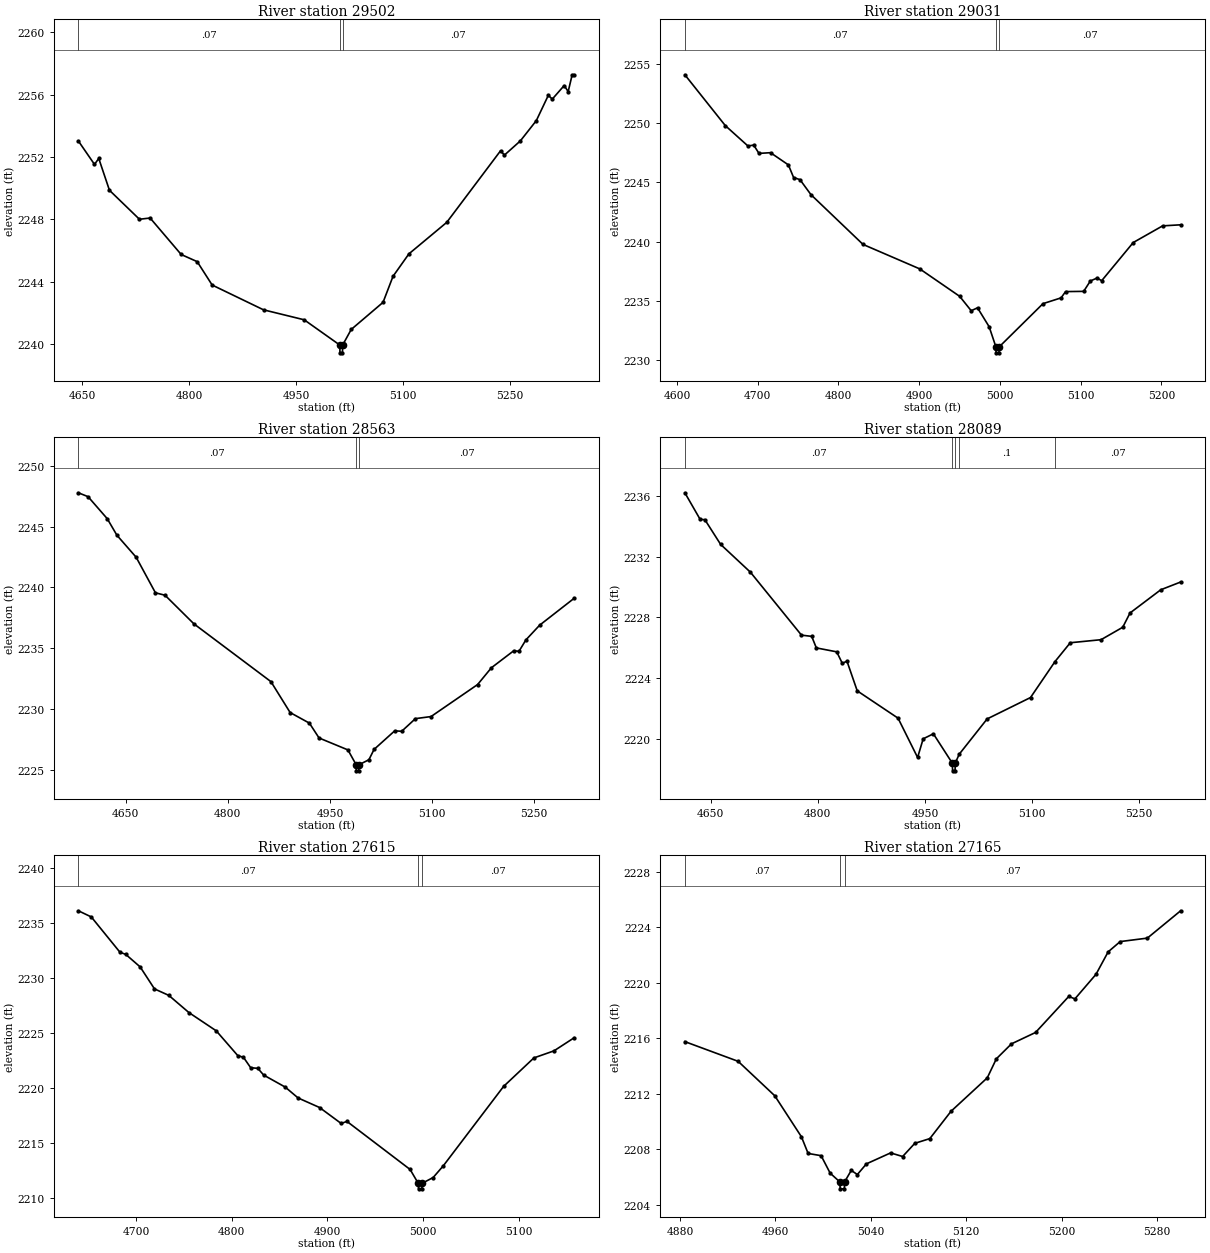
Type RM Length L Ch R = 1,29502,471,471,471
BEGIN DESCRIPTION:
Stream0262 63.0
END DESCRIPTION:
XS GIS Cut Line= 3
      1806474.96     13905775.03      1806775.00     13905575.00
      1806924.99     13905275.01
#Sta/Elev= 30
  4644.6 2253.02  4667.2 2251.52  4673.2 2251.90  4688.2 2249.86  4730.3 2248.00
  4745.3 2248.08  4788.9 2245.74  4811.4 2245.28  4832.4 2243.78  4904.5 2242.19
  4961.6 2241.55  5011.6 2239.93  5011.8 2239.43  5015.3 2239.43  5015.6 2239.93
  5027.6 2240.93  5072.3 2242.67  5086.3 2244.34  5108.6 2245.78  5161.7 2247.80
  5237.2 2252.39  5242.8 2252.12  5265.1 2253.03  5287.5 2254.33  5304.3 2255.95
  5309.9 2255.71  5326.6 2256.58  5332.2 2256.19  5337.8 2257.27  5340.6 2257.27
#Mann=3,-1,0
  4644.6    0.07       0  5011.6    0.05       0  5015.6    0.07       0
Bank Sta=5011.6,5015.6
Exp/Cntr=0.3,0.1

Type RM Length L Ch R = 1,29031,468,468,468
BEGIN DESCRIPTION:
Stream0262 62.0
END DESCRIPTION:
XS GIS Cut Line= 3
      1806824.99     13906225.02      1807075.00     13905925.00
      1807174.98     13905725.04
#Sta/Elev= 30
  4609.7 2254.11  4659.8 2249.81  4687.8 2248.09  4695.0 2248.16  4701.5 2247.46
  4715.8 2247.52  4737.9 2246.49  4744.4 2245.42  4752.3 2245.24  4765.9 2243.97
  4830.4 2239.76  4900.7 2237.69  4950.1 2235.37  4964.4 2234.15  4972.2 2234.40
  4986.6 2232.80  4995.0 2231.09  4995.2 2230.59  4998.7 2230.59  4999.0 2231.09
  5053.3 2234.75  5075.7 2235.24  5081.3 2235.77  5103.7 2235.79  5112.0 2236.67
  5120.4 2236.92  5126.0 2236.69  5165.1 2239.92  5201.5 2241.33  5223.8 2241.42
#Mann=3,-1,0
  4609.7    0.07       0  4995.0    0.05       0  4999.0    0.07       0
Bank Sta=4995,4999
Exp/Cntr=0.3,0.1

Type RM Length L Ch R = 1,28563,474,474,474
BEGIN DESCRIPTION:
Stream0262 61.0
END DESCRIPTION:
XS GIS Cut Line= 3
      1807174.99     13906425.01      1807475.00     13906125.00
      1807525.00     13905825.02
#Sta/Elev= 30
  4580.5 2247.78  4594.7 2247.46  4622.9 2245.65  4637.1 2244.29  4665.4 2242.48
  4693.7 2239.56  4707.8 2239.36  4750.2 2237.01  4863.4 2232.26  4891.6 2229.72
  4919.9 2228.85  4934.1 2227.63  4976.5 2226.65  4988.6 2225.43  4988.9 2224.93
  4992.4 2224.93  4992.6 2225.43  5007.3 2225.84  5014.9 2226.69  5045.3 2228.22
  5055.5 2228.18  5075.7 2229.22  5098.6 2229.39  5167.0 2232.02  5187.3 2233.40
  5220.2 2234.80  5227.8 2234.75  5238.0 2235.69  5258.2 2236.90  5308.9 2239.11
#Mann=3,-1,0
  4580.5    0.07       0  4988.6    0.05       0  4992.6    0.07       0
Bank Sta=4988.6,4992.6
Exp/Cntr=0.3,0.1

Type RM Length L Ch R = 1,28089,474,474,474
BEGIN DESCRIPTION:
Stream0262 60.0
END DESCRIPTION:
XS GIS Cut Line= 3
      1807625.00     13906624.99      1807875.00     13906325.00
      1807825.01     13906025.04
#Sta/Elev= 30
  4613.7 2236.20  4635.2 2234.44  4641.7 2234.43  4663.8 2232.80  4705.5 2230.97
  4777.1 2226.82  4791.4 2226.74  4797.9 2225.98  4826.5 2225.72  4834.3 2224.96
  4840.8 2225.11  4855.2 2223.15  4912.4 2221.35  4939.8 2218.76  4947.6 2219.99
  4961.9 2220.32  4988.5 2218.38  4988.8 2217.88  4992.3 2217.88  4992.5 2218.38
  4998.0 2218.97  5037.2 2221.30  5098.0 2222.71  5132.3 2225.08  5153.7 2226.32
  5196.8 2226.52  5227.2 2227.34  5237.4 2228.28  5280.5 2229.81  5308.3 2230.32
#Mann=5,-1,0
  4613.7    0.07       0  4988.5    0.05       0  4992.5    0.07       0
  4998.0     0.1       0  5132.3    0.07       0
Bank Sta=4988.5,4992.5
Exp/Cntr=0.3,0.1

Type RM Length L Ch R = 1,27615,450,450,450
BEGIN DESCRIPTION:
Stream0262 59.0
END DESCRIPTION:
XS GIS Cut Line= 3
      1808075.03     13906824.96      1808275.00     13906525.00
      1808324.99     13906375.02
#Sta/Elev= 30
  4639.6 2236.10  4653.1 2235.54  4683.1 2232.33  4689.1 2232.14  4704.2 2231.00
  4719.2 2229.00  4734.2 2228.41  4755.2 2226.85  4783.8 2225.19  4806.3 2222.94
  4812.3 2222.78  4819.8 2221.84  4827.3 2221.78  4833.4 2221.17  4855.9 2220.08
  4869.4 2219.09  4891.9 2218.22  4914.5 2216.77  4920.5 2216.96  4986.6 2212.59
  4995.1 2211.33  4995.4 2210.83  4998.9 2210.83  4999.1 2211.33  5010.7 2211.86
  5021.2 2212.91  5084.4 2220.14  5116.1 2222.73  5137.1 2223.37  5158.2 2224.56
#Mann=3,-1,0
  4639.6    0.07       0  4995.1    0.05       0  4999.1    0.07       0
Bank Sta=4995.1,4999.1
Exp/Cntr=0.3,0.1

Type RM Length L Ch R = 1,27165,427,427,427
BEGIN DESCRIPTION:
Stream0262 58.0
END DESCRIPTION:
XS GIS Cut Line= 3
      1808575.02     13906824.96      1808625.00     13906725.00
      1808675.00     13906424.99
#Sta/Elev= 30
  4884.0 2215.76  4928.7 2214.34  4959.4 2211.86  4981.8 2208.90  4987.4 2207.70
  4998.3 2207.54  5005.9 2206.28  5014.0 2205.65  5014.3 2205.15  5017.8 2205.15
  5018.0 2205.65  5023.6 2206.48  5028.7 2206.18  5036.3 2206.95  5056.6 2207.74
  5066.7 2207.48  5076.9 2208.43  5089.5 2208.77  5107.3 2210.74  5137.7 2213.15
  5145.3 2214.52  5158.0 2215.60  5178.2 2216.42  5206.1 2219.02  5211.2 2218.84
  5228.9 2220.61  5239.1 2222.23  5249.2 2222.97  5272.0 2223.22  5299.9 2225.19
#Mann=3,-1,0
  4884.0    0.07       0  5014.0    0.05       0  5018.0    0.07       0
Bank Sta=5014,5018
Exp/Cntr=0.3,0.1

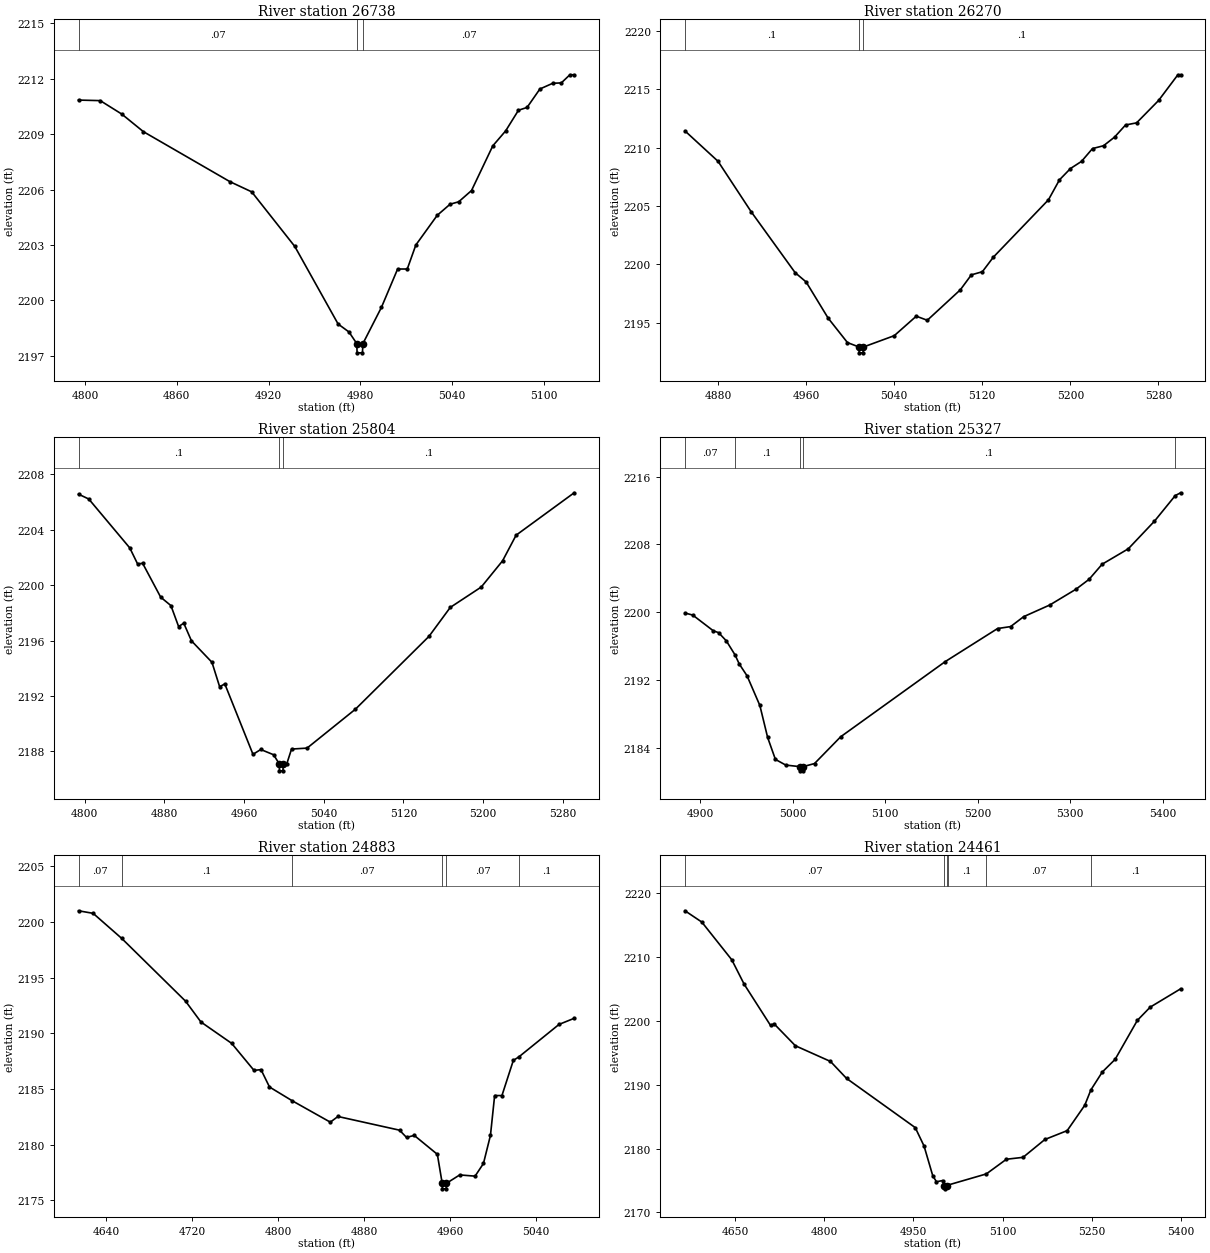
Type RM Length L Ch R = 1,26738,468,468,468
BEGIN DESCRIPTION:
Stream0262 57.0
END DESCRIPTION:
XS GIS Cut Line= 3
      1808874.99     13906975.01      1809025.00     13906825.00
      1809075.02     13906724.96
#Sta/Elev= 30
  4795.8 2210.85  4810.0 2210.82  4824.1 2210.09  4838.2 2209.14  4894.8 2206.43
  4909.0 2205.88  4937.2 2202.92  4965.5 2198.72  4972.6 2198.29  4977.7 2197.66
  4977.9 2197.16  4981.4 2197.16  4981.7 2197.66  4993.8 2199.62  5004.4 2201.70
  5010.7 2201.70  5016.3 2203.00  5030.3 2204.61  5038.7 2205.21  5044.3 2205.34
  5052.7 2205.95  5066.6 2208.37  5075.0 2209.18  5083.4 2210.30  5089.0 2210.45
  5097.4 2211.45  5105.8 2211.76  5111.4 2211.78  5117.0 2212.22  5119.8 2212.22
#Mann=3,-1,0
  4795.8    0.07       0  4977.7    0.05       0  4981.7    0.07       0
Bank Sta=4977.7,4981.7
Exp/Cntr=0.3,0.1

Type RM Length L Ch R = 1,26270,466,466,466
BEGIN DESCRIPTION:
Stream0262 56.0
END DESCRIPTION:
XS GIS Cut Line= 3
      1809425.00     13907124.99      1809425.00     13906975.00
      1809425.00     13906674.99
#Sta/Elev= 30
  4850.1 2211.43  4880.1 2208.83  4910.1 2204.52  4950.1 2199.29  4960.1 2198.49
  4980.1 2195.39  4997.6 2193.30  5008.1 2192.92  5008.3 2192.42  5011.8 2192.42
  5012.1 2192.92  5040.1 2193.89  5060.1 2195.56  5070.1 2195.21  5100.1 2197.82
  5110.1 2199.10  5120.1 2199.37  5130.1 2200.62  5180.1 2205.53  5190.1 2207.24
  5200.1 2208.21  5210.1 2208.82  5220.1 2209.92  5230.1 2210.16  5240.1 2210.90
  5250.1 2211.94  5260.1 2212.12  5280.1 2214.04  5297.6 2216.24  5300.1 2216.24
#Mann=3,-1,0
  4850.1     0.1       0  5008.1    0.05       0  5012.1     0.1       0
Bank Sta=5008.1,5012.1
Exp/Cntr=0.3,0.1

Type RM Length L Ch R = 1,25804,477,477,477
BEGIN DESCRIPTION:
Stream0262 55.0
END DESCRIPTION:
XS GIS Cut Line= 3
      1809825.00     13907125.01      1809875.00     13906925.00
      1809725.01     13906675.01
#Sta/Elev= 30
  4793.8 2206.56  4804.1 2206.21  4845.3 2202.68  4853.1 2201.53  4858.2 2201.57
  4876.3 2199.13  4886.6 2198.52  4894.3 2197.01  4899.5 2197.25  4907.2 2195.98
  4927.8 2194.43  4935.5 2192.67  4940.7 2192.87  4969.0 2187.79  4976.8 2188.14
  4989.7 2187.76  4995.4 2187.10  4995.6 2186.60  4999.1 2186.60  4999.4 2187.10
  5002.9 2187.10  5007.7 2188.17  5023.3 2188.24  5071.9 2191.05  5145.7 2196.30
  5167.1 2198.39  5198.2 2199.86  5219.6 2201.75  5233.2 2203.60  5291.5 2206.66
#Mann=3,-1,0
  4793.8     0.1       0  4995.4    0.05       0  4999.4     0.1       0
Bank Sta=4995.4,4999.4
Exp/Cntr=0.3,0.1

Type RM Length L Ch R = 1,25327,444,444,444
BEGIN DESCRIPTION:
Stream0262 54.0
END DESCRIPTION:
XS GIS Cut Line= 3
      1810225.01     13907224.99      1810275.00     13907125.00
      1810575.03     13906824.97
#Sta/Elev= 30
  4883.4 2199.89  4891.8 2199.65  4914.1 2197.79  4919.7 2197.58  4928.1 2196.61
  4937.6 2194.94  4942.1 2193.88  4950.5 2192.49  4964.4 2188.98  4972.8 2185.21
  4981.2 2182.62  4992.4 2181.95  5007.3 2181.77  5007.6 2181.27  5011.1 2181.27
  5011.3 2181.77  5023.5 2182.13  5051.8 2185.29  5164.9 2194.16  5221.5 2198.06
  5235.6 2198.29  5249.7 2199.46  5278.0 2200.84  5306.3 2202.70  5320.5 2203.87
  5334.6 2205.65  5362.9 2207.47  5391.2 2210.73  5413.7 2213.75  5419.5 2214.08
#Mann=5,-1,0
  4883.4    0.07       0  4937.6     0.1       0  5007.3    0.05       0
  5011.3     0.1       0  5413.7    0.07       0
Bank Sta=5007.3,5011.3
Exp/Cntr=0.3,0.1

Type RM Length L Ch R = 1,24883,422,422,422
BEGIN DESCRIPTION:
Stream0262 53.0
END DESCRIPTION:
XS GIS Cut Line= 3
      1810375.02     13907674.98      1810625.00     13907375.00
      1810675.00     13907325.00
#Sta/Elev= 30
  4614.1 2201.02  4627.7 2200.79  4654.4 2198.53  4713.7 2192.90  4728.0 2191.03
  4756.6 2189.11  4777.4 2186.68  4783.9 2186.75  4791.8 2185.19  4812.8 2183.96
  4848.4 2182.03  4855.5 2182.54  4912.8 2181.31  4919.3 2180.66  4926.5 2180.84
  4948.0 2179.14  4952.5 2176.54  4952.7 2176.04  4956.2 2176.04  4956.5 2176.54
  4968.8 2177.29  4983.1 2177.18  4990.9 2178.32  4997.4 2180.84  5001.3 2184.42
  5008.1 2184.42  5018.7 2187.58  5023.8 2187.89  5061.2 2190.81  5075.3 2191.36
#Mann=6,-1,0
  4614.1    0.07       0  4654.4     0.1       0  4812.8    0.07       0
  4952.5    0.05       0  4956.5    0.07       0  5023.8     0.1       0
Bank Sta=4952.5,4956.5
Exp/Cntr=0.3,0.1

Type RM Length L Ch R = 1,24461,429,429,429
BEGIN DESCRIPTION:
Stream0262 52.0
END DESCRIPTION:
XS GIS Cut Line= 3
      1810575.00     13908075.01      1810825.00     13907725.00
      1811024.98     13907375.03
#Sta/Elev= 30
  4565.9 2217.29  4594.2 2215.52  4644.6 2209.60  4665.4 2205.77  4709.7 2199.31
  4715.8 2199.55  4751.5 2196.12  4810.5 2193.66  4837.5 2191.00  4953.0 2183.28
  4967.8 2180.39  4982.5 2175.71  4988.7 2174.79  4998.9 2174.98  5001.9 2174.18
  5002.2 2173.68  5005.9 2174.18  5008.3 2174.28  5072.5 2176.02  5106.2 2178.32
  5134.2 2178.62  5170.9 2181.42  5208.4 2182.81  5237.9 2186.78  5248.2 2189.19
  5267.4 2192.00  5289.0 2193.99  5326.4 2200.11  5348.0 2202.18  5399.1 2205.05
#Mann=6,-1,0
  4565.9    0.07       0  5001.9    0.05       0  5005.9    0.07       0
  5008.3     0.1       0  5072.5    0.07       0  5248.2     0.1       0
Bank Sta=5001.9,5005.9
Exp/Cntr=0.3,0.1

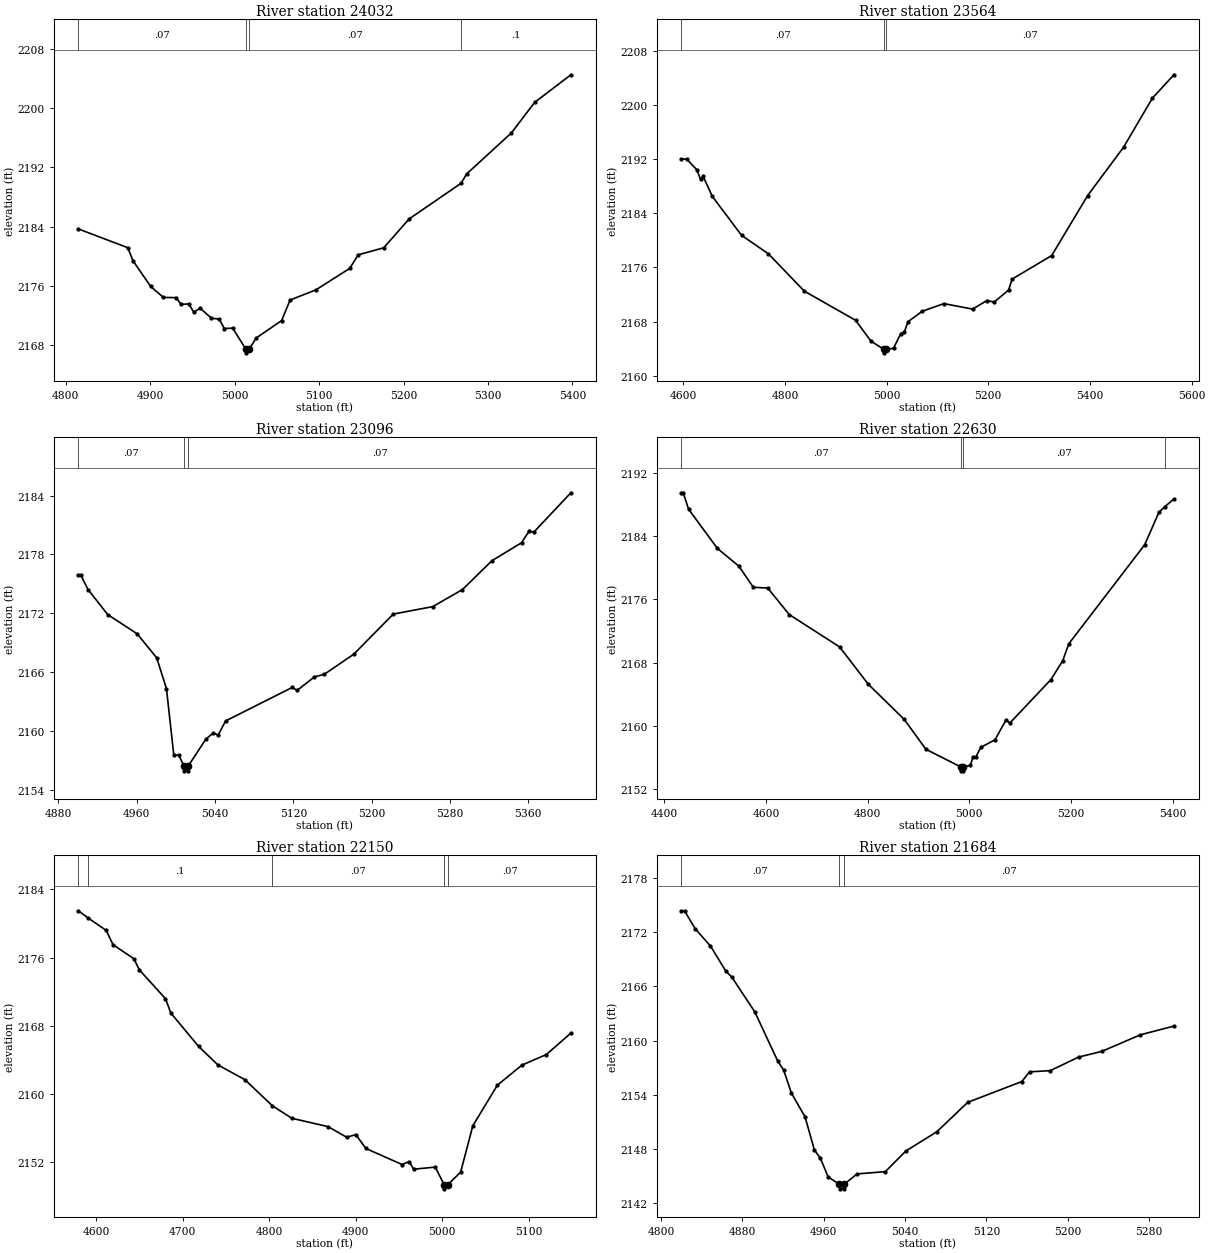
Type RM Length L Ch R = 1,24032,468,468,468
BEGIN DESCRIPTION:
Stream0262 51.0
END DESCRIPTION:
XS GIS Cut Line= 3
      1811074.99     13907925.00      1811225.00     13907825.00
      1811175.00     13907425.00
#Sta/Elev= 30
  4814.8 2183.71  4873.4 2181.18  4879.4 2179.44  4900.4 2175.97  4915.5 2174.48
  4930.5 2174.45  4936.5 2173.54  4945.5 2173.61  4951.5 2172.49  4959.0 2173.03
  4972.5 2171.67  4981.6 2171.57  4987.6 2170.29  4997.6 2170.34  5013.2 2167.51
  5013.4 2167.01  5017.3 2167.51  5025.3 2169.00  5055.6 2171.36  5065.6 2174.13
  5095.9 2175.48  5136.2 2178.39  5146.3 2180.22  5176.5 2181.17  5206.7 2185.07
  5268.1 2189.86  5274.7 2191.12  5327.7 2196.65  5355.4 2200.78  5398.2 2204.49
#Mann=4,-1,0
  4814.8    0.07       0  5013.2    0.05       0  5017.3    0.07       0
  5268.1     0.1       0
Bank Sta=5013.2,5017.3
Exp/Cntr=0.3,0.1

Type RM Length L Ch R = 1,23564,468,468,468
BEGIN DESCRIPTION:
Stream0262 50.0
END DESCRIPTION:
XS GIS Cut Line= 3
      1811625.00     13908275.02      1811675.00     13907875.00
      1812074.98     13907475.02
#Sta/Elev= 30
  4596.3 2192.00  4606.4 2192.05  4626.6 2190.45  4634.1 2189.02  4639.2 2189.47
  4656.8 2186.55  4714.7 2180.75  4767.6 2178.01  4838.2 2172.49  4939.0 2168.18
  4969.2 2165.10  4994.9 2163.87  4995.1 2163.37  4999.0 2163.87  5013.6 2164.05
  5027.7 2166.20  5034.8 2166.41  5041.9 2167.96  5070.1 2169.52  5112.6 2170.65
  5169.1 2169.84  5197.4 2171.11  5211.6 2170.88  5239.9 2172.66  5246.9 2174.28
  5324.7 2177.76  5395.4 2186.63  5466.1 2193.79  5522.7 2201.04  5565.1 2204.50
#Mann=3,-1,0
  4596.3    0.07       0  4994.9    0.05       0  4999.0    0.07       0
Bank Sta=4994.9,4999
Exp/Cntr=0.3,0.1

Type RM Length L Ch R = 1,23096,466,466,466
BEGIN DESCRIPTION:
Stream0262 49.0
END DESCRIPTION:
XS GIS Cut Line= 3
      1812075.00     13908175.01      1812075.00     13908075.00
      1812125.00     13907675.02
#Sta/Elev= 30
  4900.4 2175.87  4902.9 2175.87  4910.4 2174.40  4930.4 2171.86  4960.4 2169.90
  4980.4 2167.45  4990.4 2164.30  4997.9 2157.51  5002.9 2157.51  5008.3 2156.41
  5008.6 2155.91  5012.4 2155.91  5012.7 2156.41  5030.6 2159.14  5038.2 2159.78
  5043.2 2159.56  5050.8 2161.00  5118.8 2164.42  5123.9 2164.12  5141.5 2165.50
  5151.6 2165.76  5181.8 2167.82  5222.1 2171.91  5262.4 2172.67  5292.7 2174.41
  5322.9 2177.36  5353.1 2179.19  5360.7 2180.36  5365.7 2180.28  5403.5 2184.29
#Mann=3,-1,0
  4900.4    0.07       0  5008.3    0.05       0  5012.7    0.07       0
Bank Sta=5008.3,5012.7
Exp/Cntr=0.3,0.1

Type RM Length L Ch R = 1,22630,480,480,480
BEGIN DESCRIPTION:
Stream0262 48.0
END DESCRIPTION:
XS GIS Cut Line= 3
      1812124.97     13908425.03      1812525.00     13908025.00
      1812724.98     13907675.04
#Sta/Elev= 30
  4433.8 2189.46  4437.4 2189.46  4448.0 2187.38  4504.6 2182.43  4547.0 2180.18
  4575.3 2177.52  4603.6 2177.42  4646.0 2174.07  4745.0 2169.98  4801.5 2165.26
  4872.3 2160.81  4914.7 2157.05  4983.1 2154.82  4983.4 2154.32  4987.3 2154.32
  4987.6 2154.82  5002.4 2155.00  5007.5 2156.11  5013.2 2156.08  5022.6 2157.28
  5050.6 2158.24  5072.2 2160.73  5080.2 2160.38  5160.8 2165.86  5183.8 2168.23
  5196.0 2170.39  5345.1 2182.89  5373.1 2186.99  5384.4 2187.69  5402.6 2188.67
#Mann=4,-1,0
  4433.8    0.07       0  4983.1    0.05       0  4987.6    0.07       0
  5384.4     0.1       0
Bank Sta=4983.1,4987.6
Exp/Cntr=0.3,0.1

Type RM Length L Ch R = 1,22150,466,466,466
BEGIN DESCRIPTION:
Stream0262 47.0
END DESCRIPTION:
XS GIS Cut Line= 3
      1812774.99     13908625.04      1812925.00     13908225.00
      1813025.03     13908124.97
#Sta/Elev= 30
  4579.7 2181.48  4590.7 2180.66  4611.8 2179.18  4619.8 2177.50  4643.8 2175.86
  4650.1 2174.56  4680.3 2171.17  4686.5 2169.49  4718.6 2165.57  4740.8 2163.41
  4772.0 2161.68  4803.8 2158.61  4826.3 2157.15  4868.1 2156.17  4889.5 2154.93
  4900.1 2155.23  4911.7 2153.61  4953.5 2151.73  4961.6 2152.08  4966.9 2151.18
  4991.8 2151.43  5002.0 2149.38  5002.3 2148.88  5006.5 2149.38  5021.1 2150.84
  5035.2 2156.28  5063.5 2161.03  5091.8 2163.38  5120.1 2164.63  5148.4 2167.14
#Mann=5,-1,0
  4579.7    0.07       0  4590.7     0.1       0  4803.8    0.07       0
  5002.0    0.05       0  5006.5    0.07       0
Bank Sta=5002,5006.5
Exp/Cntr=0.3,0.1

Type RM Length L Ch R = 1,21684,450,450,450
BEGIN DESCRIPTION:
Stream0262 46.0
END DESCRIPTION:
XS GIS Cut Line= 3
      1813124.97     13908725.04      1813225.00     13908575.00
      1813275.01     13908274.97
#Sta/Elev= 30
  4819.9 2174.34  4823.0 2174.34  4833.5 2172.35  4848.5 2170.45  4863.5 2167.69
  4869.5 2167.01  4892.1 2163.17  4914.6 2157.75  4920.6 2156.71  4928.1 2154.20
  4941.6 2151.55  4950.7 2147.92  4956.7 2146.98  4964.2 2144.94  4975.4 2144.11
  4975.7 2143.61  4979.6 2143.61  4980.0 2144.11  4992.7 2145.26  5020.5 2145.51
  5040.8 2147.80  5071.2 2149.92  5101.6 2153.17  5154.8 2155.47  5162.4 2156.54
  5182.7 2156.67  5210.6 2158.17  5233.4 2158.80  5271.4 2160.63  5304.4 2161.60
#Mann=3,-1,0
  4819.9    0.07       0  4975.4    0.05       0  4980.0    0.07       0
Bank Sta=4975.4,4980
Exp/Cntr=0.3,0.1

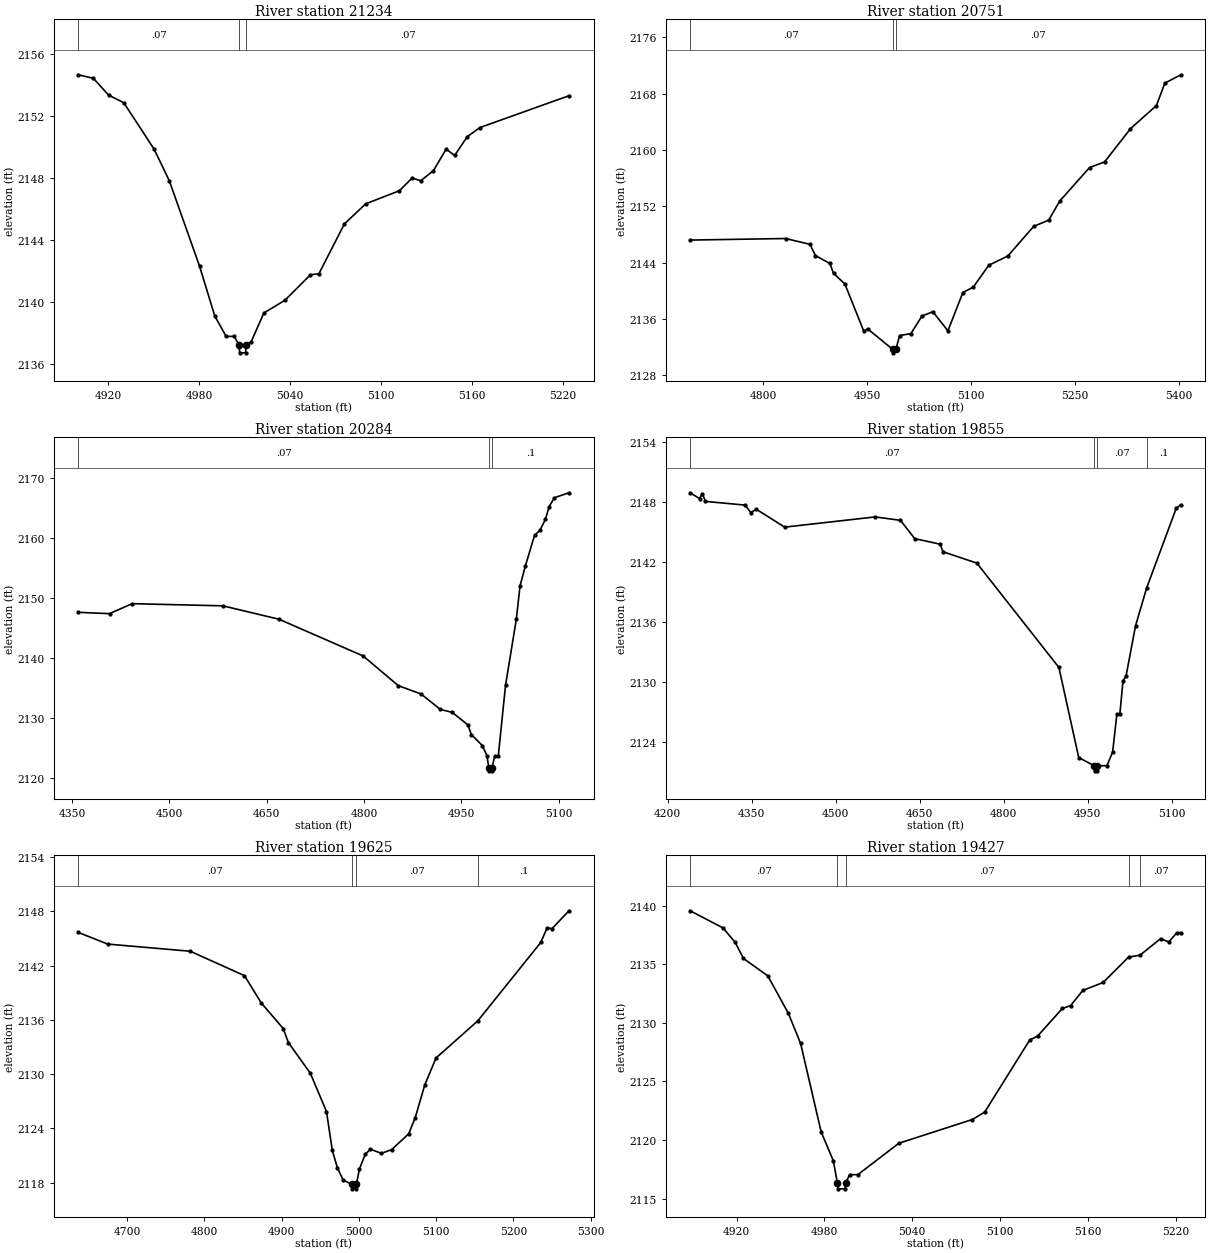
Type RM Length L Ch R = 1,21234,483,483,483
BEGIN DESCRIPTION:
Stream0262 45.0
END DESCRIPTION:
XS GIS Cut Line= 3
      1813625.00     13908725.01      1813625.00     13908625.00
      1813525.01     13908425.02
#Sta/Elev= 30
  4900.3 2154.64  4910.3 2154.41  4920.3 2153.33  4930.3 2152.84  4950.3 2149.85
  4960.3 2147.82  4980.3 2142.30  4990.3 2139.10  4997.8 2137.78  5003.1 2137.78
  5006.4 2137.22  5006.7 2136.72  5010.6 2136.72  5011.0 2137.22  5014.3 2137.43
  5022.7 2139.29  5036.6 2140.11  5053.4 2141.75  5059.0 2141.82  5075.8 2145.03
  5089.8 2146.32  5112.1 2147.17  5120.5 2147.99  5126.1 2147.81  5134.5 2148.46
  5142.9 2149.85  5148.5 2149.44  5156.8 2150.65  5165.2 2151.24  5223.9 2153.29
#Mann=3,-1,0
  4900.3    0.07       0  5006.4    0.05       0  5011.0    0.07       0
Bank Sta=5006.4,5011
Exp/Cntr=0.3,0.1

Type RM Length L Ch R = 1,20751,467,467,467
BEGIN DESCRIPTION:
Stream0262 44.0
END DESCRIPTION:
XS GIS Cut Line= 4
      1813911.68     13908776.19      1814046.87     13908616.54
      1814075.00     13908525.00      1814275.01     13908174.98
#Sta/Elev= 30
  4694.6 2147.21  4832.5 2147.43  4867.6 2146.60  4875.4 2145.00  4896.2 2143.89
  4901.5 2142.48  4917.8 2140.99  4945.3 2134.25  4950.5 2134.63  4986.8 2131.71
  4987.1 2131.21  4991.4 2131.71  4996.9 2133.66  5013.2 2133.94  5029.1 2136.44
  5044.9 2137.04  5066.5 2134.33  5088.1 2139.76  5103.2 2140.54  5125.5 2143.64
  5152.9 2144.94  5190.3 2149.15  5211.9 2150.03  5227.8 2152.73  5270.9 2157.50
  5292.5 2158.29  5330.0 2163.01  5367.4 2166.30  5379.6 2169.48  5402.7 2170.66
#Mann=3,-1,0
  4694.6    0.07       0  4986.8    0.05       0  4991.4    0.07       0
Bank Sta=4986.8,4991.4
Exp/Cntr=0.3,0.1

Type RM Length L Ch R = 1,20284,429,429,429
BEGIN DESCRIPTION:
Stream0262 43.0
END DESCRIPTION:
XS GIS Cut Line= 3
      1813928.75     13908819.65      1814525.00     13908575.00
      1814625.00     13908525.00
#Sta/Elev= 30
  4359.6 2147.61  4407.8 2147.39  4442.6 2149.05  4582.5 2148.69  4669.0 2146.46
  4798.7 2140.35  4852.8 2135.42  4888.1 2134.02  4917.6 2131.46  4936.0 2130.97
  4960.0 2128.90  4965.4 2127.29  4982.5 2125.43  4989.4 2123.80  4992.4 2121.75
  4992.8 2121.25  4996.9 2121.25  4997.2 2121.75  5001.4 2123.68  5006.9 2123.68
  5018.1 2135.46  5034.8 2146.51  5040.4 2151.98  5048.8 2155.35  5062.8 2160.41
  5071.2 2161.26  5079.6 2163.07  5085.2 2165.17  5093.5 2166.67  5115.9 2167.49
#Mann=3,-1,0
  4359.6    0.07       0  4992.4    0.05       0  4997.2     0.1       0
Bank Sta=4992.4,4997.2
Exp/Cntr=0.3,0.1

Type RM Length L Ch R = 1,19855,230,230,230
BEGIN DESCRIPTION:
Stream0262 42.0
END DESCRIPTION:
XS GIS Cut Line= 3
      1813867.86     13908867.00      1814625.00     13908975.00
      1814724.99     13908925.00
#Sta/Elev= 30
  4240.1 2148.90  4256.8 2148.32  4261.9 2148.80  4267.5 2148.04  4338.2 2147.67
  4348.3 2146.93  4358.4 2147.25  4408.9 2145.47  4570.6 2146.49  4615.7 2146.15
  4641.3 2144.32  4686.5 2143.77  4691.8 2143.01  4752.2 2141.88  4898.8 2131.46
  4934.2 2122.47  4962.0 2121.64  4962.4 2121.14  4966.5 2121.14  4966.9 2121.64
  4984.7 2121.66  4994.8 2123.02  5002.4 2126.83  5007.7 2126.83  5013.3 2130.12
  5018.9 2130.64  5035.7 2135.62  5055.7 2139.42  5108.3 2147.34  5116.7 2147.71
#Mann=4,-1,0
  4240.1    0.07       0  4962.0    0.05       0  4966.9    0.07       0
  5055.7     0.1       0
Bank Sta=4962,4966.9
Exp/Cntr=0.3,0.1

Type RM Length L Ch R = 1,19625,198,198,198
BEGIN DESCRIPTION:
Stream0262 41.1
END DESCRIPTION:
XS GIS Cut Line= 3
      1814347.30     13909411.50      1814648.98     13909138.04
      1814785.67     13908955.78
#Sta/Elev= 30
  4637.0 2145.66  4675.1 2144.37  4781.9 2143.58  4852.1 2140.88  4873.8 2137.87
  4902.2 2135.04  4908.9 2133.49  4937.3 2130.10  4958.2 2125.87  4965.7 2121.59
  4972.4 2119.63  4979.9 2118.28  4991.2 2117.83  4991.7 2117.33  4996.5 2117.33
  4996.9 2117.83  5000.8 2119.52  5008.3 2121.13  5015.0 2121.71  5029.2 2121.25
  5042.7 2121.67  5064.6 2123.41  5073.0 2125.19  5085.5 2128.84  5100.0 2131.79
  5153.9 2135.88  5235.5 2144.55  5243.8 2146.19  5250.0 2146.07  5272.0 2148.05
#Mann=4,-1,0
  4637.0    0.07       0  4991.2    0.05       0  4996.9    0.07       0
  5153.9     0.1       0
Bank Sta=4991.2,4996.9
Exp/Cntr=0.3,0.1

Type RM Length L Ch R = 1,19427,448,448,448
BEGIN DESCRIPTION:
Stream0262 41.0
END DESCRIPTION:
XS GIS Cut Line= 3
      1814624.96     13909375.02      1814725.00     13909325.00
      1814824.98     13909125.04
#Sta/Elev= 30
  4888.2 2139.57  4910.6 2138.11  4919.0 2136.87  4924.6 2135.50  4941.3 2134.01
  4955.3 2130.82  4963.7 2128.24  4977.7 2120.71  4986.1 2118.21  4988.8 2116.33
  4989.3 2115.83  4994.1 2115.83  4994.5 2116.33  4997.2 2117.04  5002.8 2117.04
  5030.8 2119.72  5081.1 2121.75  5089.5 2122.38  5120.2 2128.52  5125.8 2128.89
  5142.6 2131.23  5148.2 2131.47  5156.6 2132.77  5170.5 2133.45  5187.8 2135.61
  5195.7 2135.78  5209.7 2137.19  5215.3 2136.91  5220.9 2137.70  5223.6 2137.70
#Mann=5,-1,0
  4888.2    0.07       0  4988.8    0.05       0  4994.5    0.07       0
  5187.8     0.1       0  5195.7    0.07       0
Bank Sta=4988.8,4994.5
Exp/Cntr=0.3,0.1

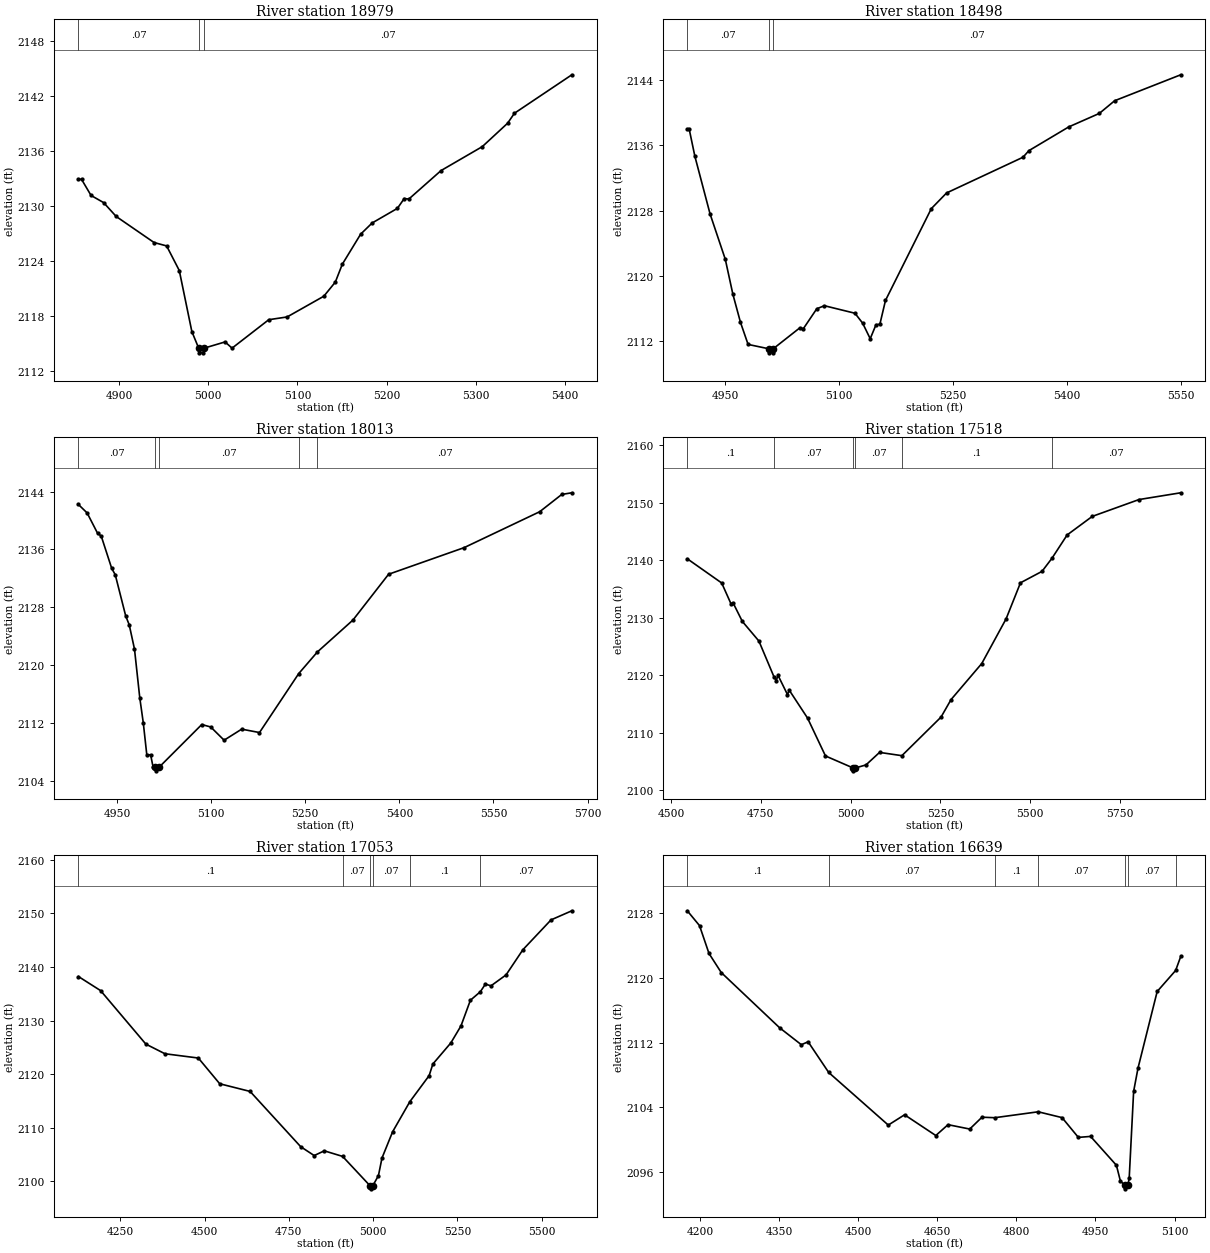
Type RM Length L Ch R = 1,18979,481,481,481
BEGIN DESCRIPTION:
Stream0262 40.0
END DESCRIPTION:
XS GIS Cut Line= 3
      1814974.99     13909675.01      1815075.00     13909575.00
      1815174.99     13909175.04
#Sta/Elev= 30
  4854.2 2132.94  4857.7 2132.94  4868.4 2131.18  4882.5 2130.40  4896.6 2128.89
  4939.1 2126.05  4953.2 2125.68  4967.4 2123.00  4981.5 2116.35  4989.2 2114.53
  4989.7 2114.03  4994.5 2114.03  4994.9 2114.53  5018.8 2115.22  5026.6 2114.54
  5067.8 2117.64  5088.4 2117.94  5129.6 2120.20  5142.5 2121.74  5150.3 2123.68
  5170.9 2126.96  5183.8 2128.18  5212.1 2129.77  5219.8 2130.84  5225.0 2130.79
  5261.1 2133.89  5307.4 2136.50  5335.8 2139.05  5343.5 2140.14  5407.9 2144.33
#Mann=3,-1,0
  4854.2    0.07       0  4989.2    0.05       0  4994.9    0.07       0
Bank Sta=4989.2,4994.9
Exp/Cntr=0.3,0.1

Type RM Length L Ch R = 1,18498,485,485,485
BEGIN DESCRIPTION:
Stream0262 39.0
END DESCRIPTION:
XS GIS Cut Line= 3
      1815525.00     13909775.01      1815525.00     13909675.00
      1815470.41     13909128.43
#Sta/Elev= 30
  4900.0 2137.97  4902.5 2137.97  4910.0 2134.63  4930.0 2127.57  4950.0 2122.03
  4960.0 2117.74  4970.0 2114.30  4980.0 2111.60  5007.1 2111.07  5007.6 2110.57
  5012.6 2110.57  5013.1 2111.07  5047.8 2113.61  5052.8 2113.54  5070.4 2115.97
  5080.4 2116.34  5120.6 2115.42  5130.7 2114.21  5140.7 2112.30  5148.3 2114.01
  5153.4 2114.07  5160.8 2116.99  5221.1 2128.23  5241.2 2130.15  5341.7 2134.52
  5349.5 2135.33  5402.0 2138.24  5442.2 2139.89  5462.3 2141.44  5549.3 2144.62
#Mann=3,-1,0
  4900.0    0.07       0  5007.1    0.05       0  5013.1    0.07       0
Bank Sta=5007.1,5013.1
Exp/Cntr=0.3,0.1

Type RM Length L Ch R = 1,18013,495,495,495
BEGIN DESCRIPTION:
Stream0262 38.0
END DESCRIPTION:
XS GIS Cut Line= 3
      1816024.98     13909674.97      1815975.00     13909575.00
      1815526.87     13909070.71
#Sta/Elev= 30
  4888.5 2142.21  4902.4 2141.04  4919.2 2138.20  4924.8 2137.86  4941.6 2133.36
  4947.2 2132.49  4963.9 2126.78  4969.5 2125.55  4977.9 2122.19  4986.3 2115.45
  4991.9 2111.99  4997.5 2107.56  5003.6 2107.56  5007.4 2105.92  5011.1 2105.84
  5011.6 2105.34  5017.1 2105.84  5085.1 2111.75  5099.4 2111.41  5120.7 2109.58
  5148.7 2111.11  5177.1 2110.64  5239.6 2118.80  5269.4 2121.80  5326.0 2126.21
  5382.8 2132.55  5503.3 2136.24  5623.7 2141.21  5658.8 2143.60  5674.9 2143.83
#Mann=5,-1,0
  4888.5    0.07       0  5011.1    0.05       0  5017.1    0.07       0
  5239.6     0.1       0  5269.4    0.07       0
Bank Sta=5011.1,5017.1
Exp/Cntr=0.3,0.1

Type RM Length L Ch R = 1,17518,465,465,465
BEGIN DESCRIPTION:
Stream0262 37.0
END DESCRIPTION:
XS GIS Cut Line= 5
      1816230.31     13909663.91      1816327.17     13909378.33
      1816325.00     13909225.00      1816275.00     13908825.00
      1816267.76     13908308.66
#Sta/Elev= 30
  4545.1 2140.24  4640.9 2136.03  4667.0 2132.38  4672.3 2132.61  4698.4 2129.34
  4744.6 2125.92  4786.5 2119.70  4792.7 2119.03  4797.9 2119.94  4824.1 2116.61
  4829.3 2117.35  4880.0 2112.52  4930.0 2105.92  5007.0 2103.83  5007.5 2103.33
  5013.1 2103.83  5042.8 2104.36  5080.6 2106.54  5142.8 2105.97  5251.9 2112.69
  5279.7 2115.73  5365.3 2122.01  5433.1 2129.79  5473.1 2136.06  5533.1 2138.05
  5560.7 2140.32  5603.1 2144.39  5673.1 2147.62  5803.2 2150.55  5919.5 2151.73
#Mann=6,-1,0
  4545.1     0.1       0  4786.5    0.07       0  5007.0    0.05       0
  5013.1    0.07       0  5142.8     0.1       0  5560.7    0.07       0
Bank Sta=5007,5013.1
Exp/Cntr=0.3,0.1

Type RM Length L Ch R = 1,17053,414,414,414
BEGIN DESCRIPTION:
Stream0262 36.0
END DESCRIPTION:
XS GIS Cut Line= 5
      1816325.66     13909668.72      1816665.61     13909310.74
      1816675.00     13908925.00      1816625.00     13908775.00
      1816432.00     13908394.95
#Sta/Elev= 30
  4125.8 2138.22  4191.6 2135.59  4325.9 2125.61  4382.5 2123.81  4481.6 2123.01
  4545.1 2118.21  4635.2 2116.78  4785.3 2106.47  4825.3 2104.82  4855.3 2105.70
  4909.6 2104.66  4992.1 2099.11  4992.6 2098.61  4998.5 2099.11  5015.9 2101.08
  5026.4 2104.35  5058.0 2109.26  5109.0 2114.86  5166.3 2119.73  5177.4 2121.90
  5230.7 2125.83  5260.8 2129.01  5288.7 2133.79  5318.1 2135.37  5333.2 2136.80
  5349.8 2136.48  5394.4 2138.51  5444.5 2143.22  5527.9 2148.78  5589.7 2150.48
#Mann=6,-1,0
  4125.8     0.1       0  4909.6    0.07       0  4992.1    0.05       0
  4998.5    0.07       0  5109.0     0.1       0  5318.1    0.07       0
Bank Sta=4992.1,4998.5
Exp/Cntr=0.3,0.1

Type RM Length L Ch R = 1,16639,675,675,675
BEGIN DESCRIPTION:
Stream0262 35.0
END DESCRIPTION:
XS GIS Cut Line= 3
      1817225.00     13909574.98      1817025.00     13908775.00
      1816975.00     13908675.00
#Sta/Elev= 30
  4175.4 2128.28  4198.6 2126.45  4216.6 2123.01  4239.8 2120.66  4350.6 2113.84
  4391.8 2111.75  4404.7 2112.11  4443.8 2108.32  4556.8 2101.83  4587.7 2103.10
  4647.0 2100.54  4670.2 2101.88  4711.4 2101.34  4734.6 2102.80  4758.9 2102.74
  4841.3 2103.47  4886.6 2102.75  4917.5 2100.31  4940.7 2100.43  4989.7 2096.87
  4997.4 2094.90  5005.1 2094.46  5005.6 2093.96  5011.6 2094.46  5014.0 2095.29
  5022.4 2105.99  5030.7 2108.86  5067.1 2118.32  5102.1 2120.91  5111.8 2122.64
#Mann=7,-1,0
  4175.4     0.1       0  4443.8    0.07       0  4758.9     0.1       0
  4841.3    0.07       0  5005.1    0.05       0  5011.6    0.07       0
  5102.1     0.1       0
Bank Sta=5005.1,5011.6
Exp/Cntr=0.3,0.1