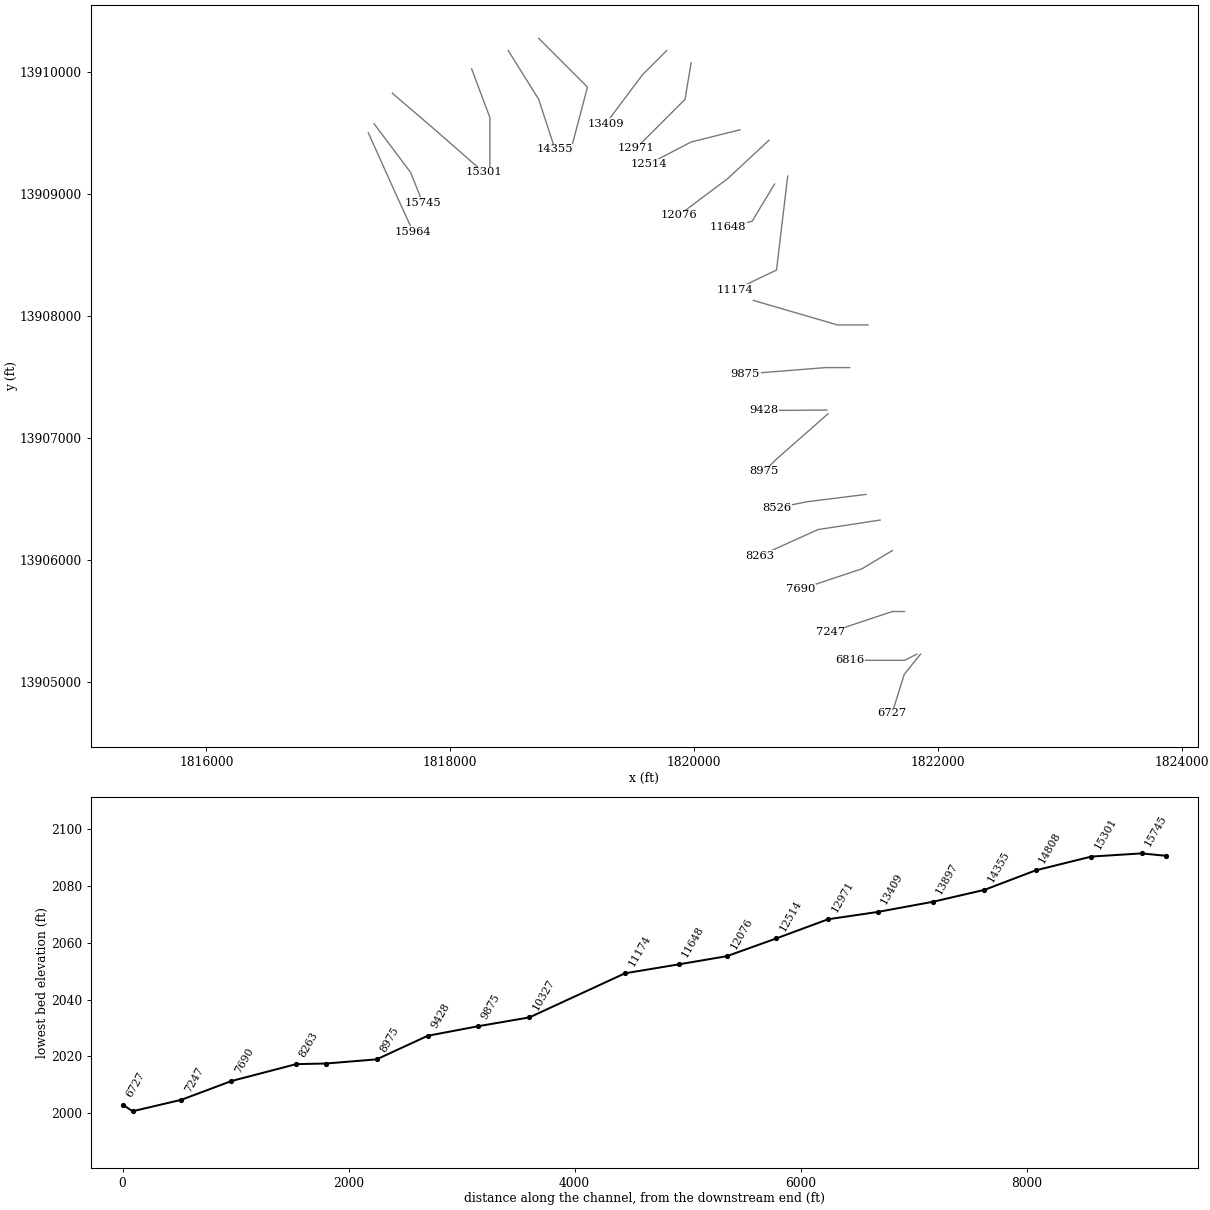
HEC-RAS study Stream0262.prj: Stream0262 Base Level Engineering

--- Stream0262.g01 (geometry) --- (continued)

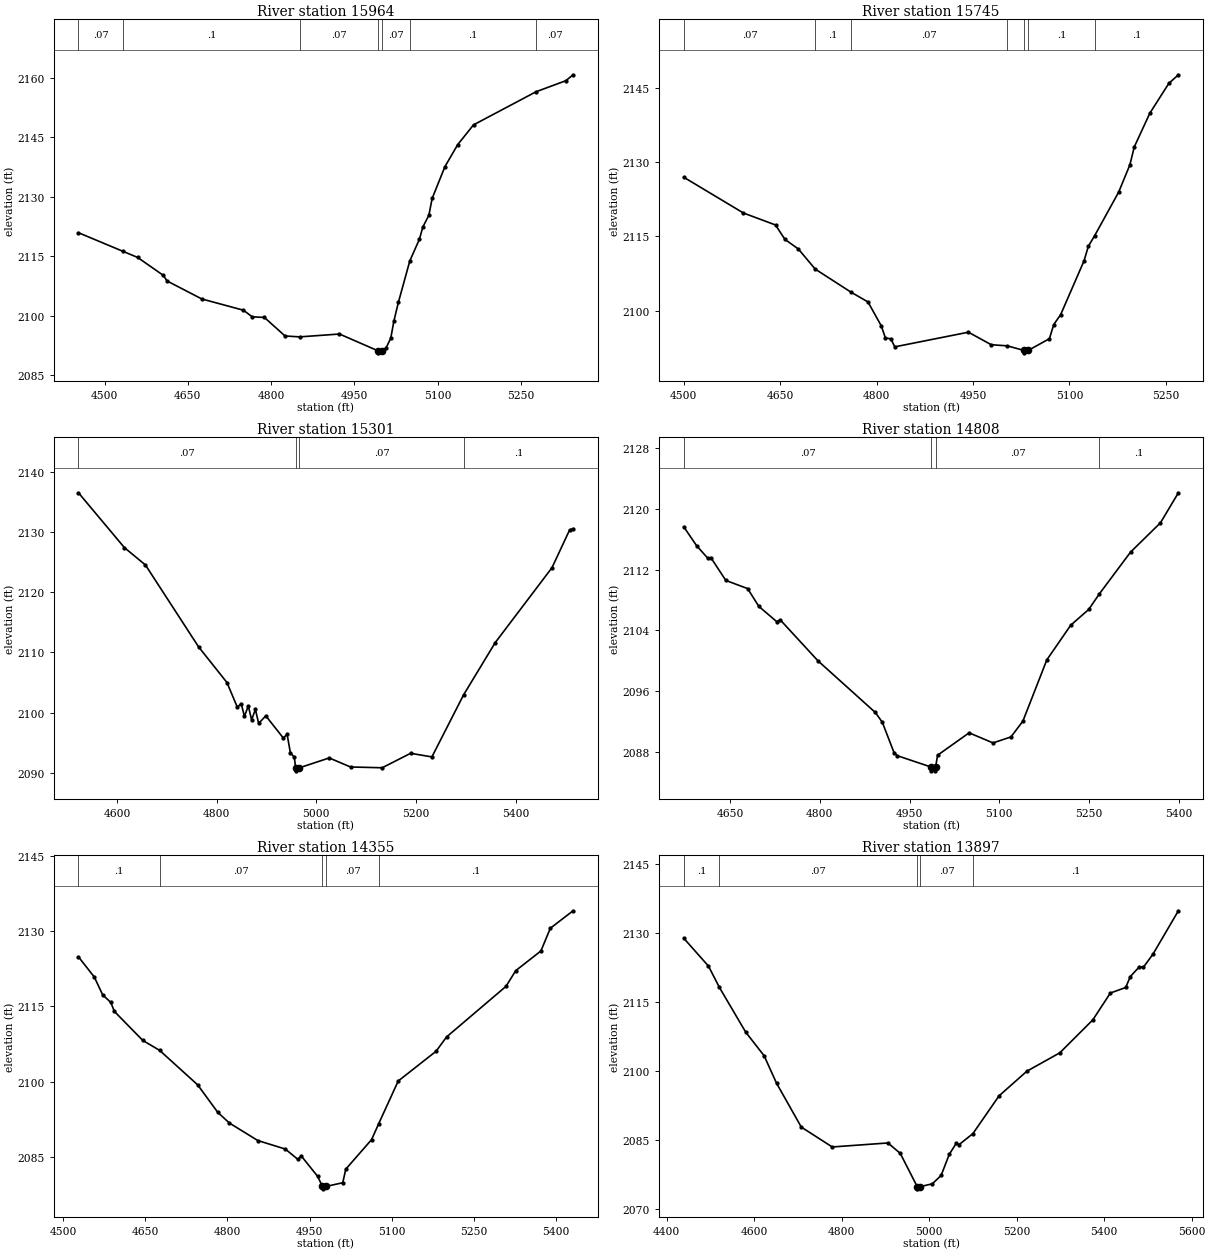
Type RM Length L Ch R = 1,15964,219,219,219
BEGIN DESCRIPTION:
Stream0262 34.0
END DESCRIPTION:
XS GIS Cut Line= 3
      1817327.81     13909500.56      1817551.46     13909003.29
      1817695.60     13908688.80
#Sta/Elev= 30
  4453.0 2120.93  4533.4 2116.22  4559.6 2114.69  4605.9 2110.16  4612.6 2108.75
  4675.3 2104.20  4750.3 2101.36  4766.1 2099.69  4788.0 2099.54  4825.2 2094.86
  4851.6 2094.63  4923.3 2095.35  4992.9 2091.10  4993.4 2090.60  5000.1 2091.10
  5007.4 2091.88  5015.8 2094.33  5021.3 2098.60  5029.4 2103.32  5050.1 2113.84
  5067.3 2119.27  5073.4 2122.33  5084.4 2125.35  5090.3 2129.59  5113.3 2137.61
  5136.3 2143.17  5164.8 2148.16  5277.6 2156.53  5331.3 2159.32  5344.2 2160.81
#Mann=7,-1,0
  4453.0    0.07       0  4533.4     0.1       0  4851.6    0.07       0
  4992.9    0.05       0  5000.1    0.07       0  5050.1     0.1       0
  5277.6    0.07       0
Bank Sta=4992.9,5000.1
Exp/Cntr=0.3,0.1

Type RM Length L Ch R = 1,15745,444,444,444
BEGIN DESCRIPTION:
Stream0262 33.0
END DESCRIPTION:
XS GIS Cut Line= 3
      1817374.98     13909575.03      1817675.00     13909175.00
      1817775.00     13908925.00
#Sta/Elev= 30
  4500.2 2126.92  4592.9 2119.70  4642.9 2117.28  4657.5 2114.37  4678.4 2112.43
  4704.6 2108.37  4760.0 2103.73  4786.7 2101.73  4807.5 2096.87  4813.8 2094.45
  4822.1 2094.29  4828.4 2092.66  4942.9 2095.62  4978.4 2093.09  5003.4 2092.86
  5028.9 2091.95  5029.4 2091.45  5036.1 2091.95  5068.9 2094.31  5075.6 2097.16
  5086.4 2099.17  5122.7 2110.02  5129.5 2112.99  5139.1 2115.08  5176.6 2123.91
  5194.1 2129.44  5200.8 2133.02  5225.1 2139.86  5254.7 2145.89  5269.5 2147.62
#Mann=7,-1,0
  4500.2    0.07       0  4704.6     0.1       0  4760.0    0.07       0
  5003.4     0.1       0  5028.9    0.05       0  5036.1     0.1       0
  5139.1     0.1       0
Bank Sta=5028.9,5036.1
Exp/Cntr=0.3,0.1

Type RM Length L Ch R = 1,15301,493,493,493
BEGIN DESCRIPTION:
Stream0262 32.0
END DESCRIPTION:
XS GIS Cut Line= 3
      1817525.01     13909824.99      1817875.00     13909525.00
      1818275.02     13909174.98
#Sta/Elev= 30
  4522.6 2136.48  4614.8 2127.38  4657.0 2124.50  4763.5 2110.93  4820.6 2104.99
  4841.4 2100.90  4849.1 2101.50  4855.7 2099.37  4863.4 2101.13  4870.0 2098.80
  4877.7 2100.52  4884.2 2098.21  4898.5 2099.47  4933.6 2095.79  4941.3 2096.39
  4947.9 2093.31  4955.6 2092.63  4958.5 2090.84  4959.0 2090.34  4965.8 2090.84
  5025.8 2092.48  5068.5 2090.98  5132.1 2090.85  5189.1 2093.25  5231.8 2092.65
  5295.5 2102.96  5358.9 2111.62  5472.8 2124.05  5508.0 2130.28  5515.1 2130.53
#Mann=4,-1,0
  4522.6    0.07       0  4958.5    0.05       0  4965.8    0.07       0
  5295.5     0.1       0
Bank Sta=4958.5,4965.8
Exp/Cntr=0.3,0.1

Type RM Length L Ch R = 1,14808,453,453,453
BEGIN DESCRIPTION:
Stream0262 31.0
END DESCRIPTION:
XS GIS Cut Line= 3
      1818174.99     13910025.01      1818325.00     13909625.00
      1818325.00     13909225.02
#Sta/Elev= 30
  4572.4 2117.64  4593.8 2115.16  4612.5 2113.51  4617.8 2113.57  4642.7 2110.58
  4679.2 2109.50  4697.9 2107.16  4728.2 2105.12  4733.5 2105.40  4796.7 2099.99
  4892.8 2093.17  4904.4 2091.89  4924.0 2087.89  4929.3 2087.48  4986.1 2085.98
  4986.6 2085.48  4993.0 2085.48  4993.5 2085.98  4996.9 2087.54  5049.6 2090.49
  5089.6 2089.16  5119.6 2089.95  5139.6 2092.04  5179.6 2100.11  5219.6 2104.68
  5249.6 2106.75  5267.5 2108.81  5319.6 2114.31  5369.6 2118.17  5399.6 2122.13
#Mann=4,-1,0
  4572.4    0.07       0  4986.1    0.05       0  4993.5    0.07       0
  5267.5     0.1       0
Bank Sta=4986.1,4993.5
Exp/Cntr=0.3,0.1

Type RM Length L Ch R = 1,14355,458,458,458
BEGIN DESCRIPTION:
Stream0262 30.0
END DESCRIPTION:
XS GIS Cut Line= 3
      1818474.99     13910175.02      1818725.00     13909775.00
      1818858.58     13909365.56
#Sta/Elev= 30
  4528.3 2124.85  4557.2 2120.83  4572.5 2117.27  4587.3 2115.77  4593.8 2113.98
  4645.7 2108.19  4676.2 2106.23  4745.9 2099.33  4782.4 2093.87  4803.7 2091.73
  4855.6 2088.24  4905.7 2086.55  4928.7 2084.48  4934.6 2085.20  4964.6 2081.12
  4973.3 2079.12  4973.8 2078.62  4980.8 2079.12  5010.5 2079.84  5016.0 2082.54
  5063.1 2088.43  5076.2 2091.63  5111.7 2100.11  5180.7 2106.03  5199.9 2108.89
  5308.3 2118.97  5326.1 2122.10  5372.1 2126.03  5389.2 2130.55  5430.7 2134.03
#Mann=5,-1,0
  4528.3     0.1       0  4676.2    0.07       0  4973.3    0.05       0
  4980.8    0.07       0  5076.2     0.1       0
Bank Sta=4973.3,4980.8
Exp/Cntr=0.3,0.1

Type RM Length L Ch R = 1,13897,488,488,488
BEGIN DESCRIPTION:
Stream0262 29.0
END DESCRIPTION:
XS GIS Cut Line= 3
      1818725.03     13910274.97      1819125.00     13909875.00
      1818980.54     13909328.62
#Sta/Elev= 30
  4438.9 2128.92  4495.4 2122.86  4520.2 2118.25  4580.3 2108.53  4622.7 2103.34
  4651.0 2097.38  4707.6 2087.84  4778.3 2083.52  4905.6 2084.39  4933.8 2082.13
  4972.5 2074.91  4973.0 2074.41  4980.1 2074.91  5007.1 2075.50  5027.3 2077.33
  5045.9 2081.92  5062.3 2084.38  5067.5 2083.97  5099.9 2086.42  5159.7 2094.64
  5223.3 2100.00  5298.6 2104.00  5374.0 2111.16  5414.2 2117.01  5449.3 2118.21
  5459.7 2120.58  5480.4 2122.71  5489.5 2122.59  5511.4 2125.43  5569.7 2134.90
#Mann=5,-1,0
  4438.9     0.1       0  4520.2    0.07       0  4972.5    0.05       0
  4980.1    0.07       0  5099.9     0.1       0
Bank Sta=4972.5,4980.1
Exp/Cntr=0.3,0.1

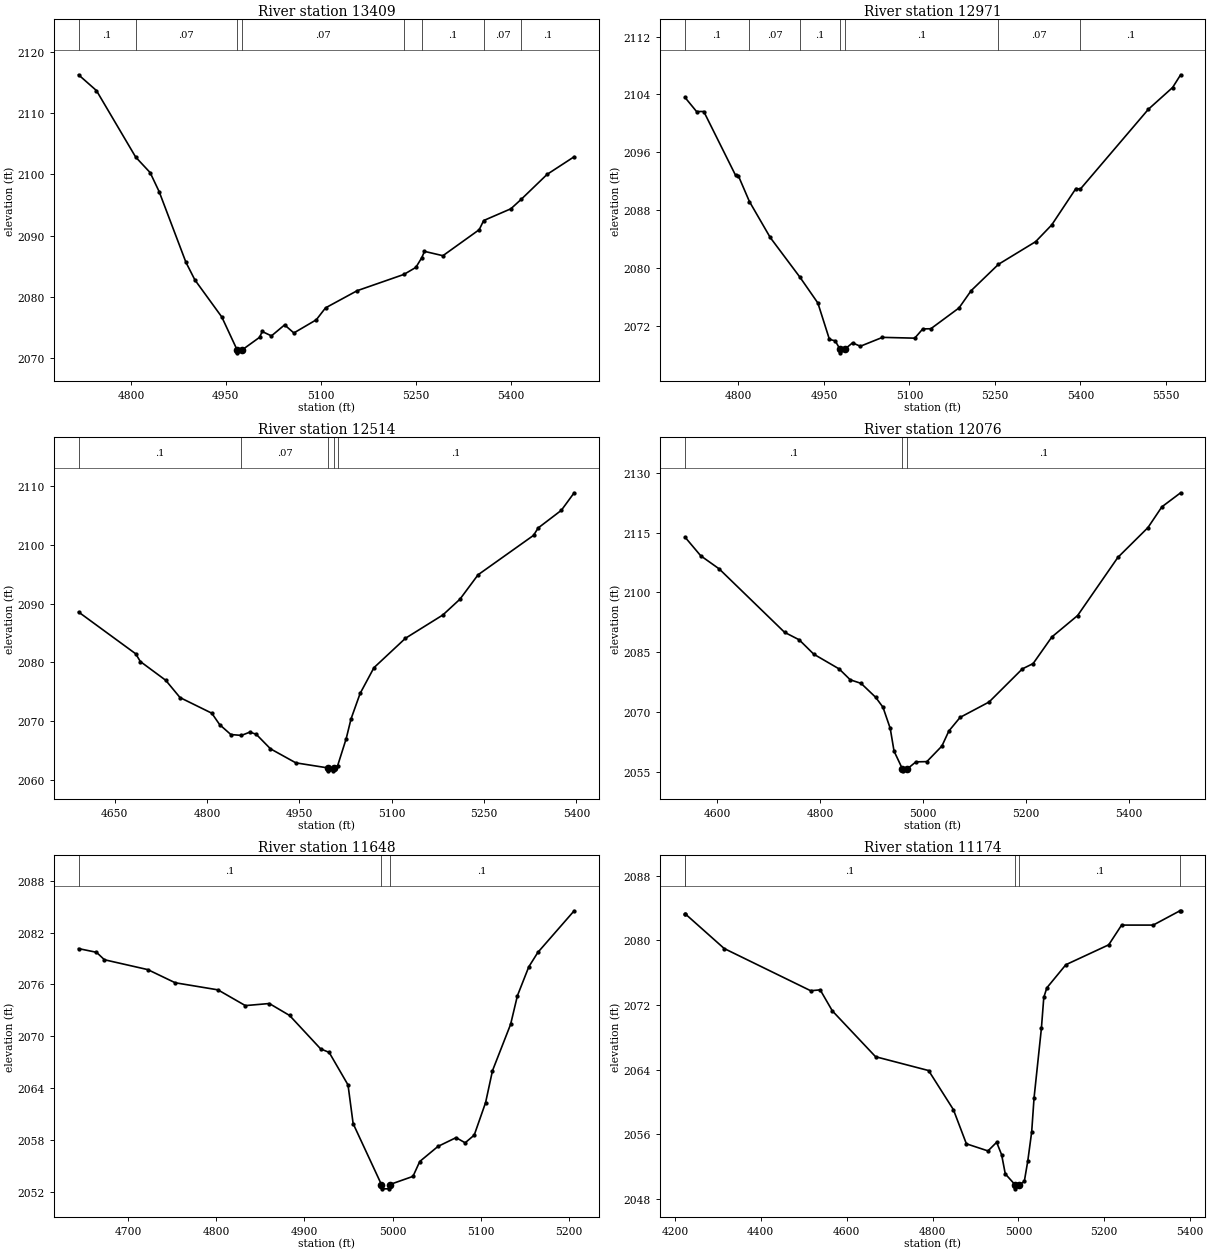
Type RM Length L Ch R = 1,13409,438,438,438
BEGIN DESCRIPTION:
Stream0262 28.0
END DESCRIPTION:
XS GIS Cut Line= 3
      1819774.99     13910174.99      1819575.00     13909975.00
      1819275.02     13909575.02
#Sta/Elev= 30
  4717.3 2116.29  4745.6 2113.71  4807.6 2102.83  4830.4 2100.30  4844.6 2097.20
  4887.0 2085.62  4901.1 2082.75  4943.6 2076.69  4967.7 2071.33  4968.2 2070.83
  4976.0 2071.33  5003.3 2073.37  5007.4 2074.32  5022.0 2073.60  5042.8 2075.40
  5057.4 2074.08  5092.8 2076.23  5107.4 2078.18  5157.4 2080.99  5231.2 2083.65
  5250.1 2084.80  5259.4 2086.38  5263.7 2087.42  5292.8 2086.71  5350.1 2090.96
  5357.2 2092.46  5400.1 2094.38  5416.8 2095.96  5457.4 2100.01  5500.1 2102.89
#Mann=8,-1,0
  4717.3     0.1       0  4807.6    0.07       0  4967.7    0.05       0
  4976.0    0.07       0  5231.2    0.07       0  5259.4     0.1       0
  5357.2    0.07       0  5416.8     0.1       0
Bank Sta=4967.7,4976
Exp/Cntr=0.3,0.1

Type RM Length L Ch R = 1,12971,457,457,457
BEGIN DESCRIPTION:
Stream0262 27.0
END DESCRIPTION:
XS GIS Cut Line= 3
      1819975.00     13910075.02      1819925.00     13909775.00
      1819525.03     13909375.03
#Sta/Elev= 30
  4706.1 2103.59  4726.4 2101.64  4739.1 2101.64  4794.8 2092.83  4799.9 2092.73
  4819.2 2089.19  4855.7 2084.22  4908.2 2078.69  4939.3 2075.16  4959.6 2070.13
  4969.7 2069.93  4978.2 2068.77  4978.7 2068.27  4986.5 2068.77  5000.1 2069.65
  5013.8 2069.18  5052.7 2070.41  5109.3 2070.30  5123.4 2071.58  5137.5 2071.60
  5187.0 2074.48  5208.3 2076.87  5256.2 2080.51  5321.4 2083.64  5349.7 2085.96
  5392.1 2090.99  5400.0 2090.92  5519.4 2101.96  5561.8 2104.96  5575.9 2106.72
#Mann=7,-1,0
  4706.1     0.1       0  4819.2    0.07       0  4908.2     0.1       0
  4978.2    0.05       0  4986.5     0.1       0  5256.2    0.07       0
  5400.0     0.1       0
Bank Sta=4978.2,4986.5
Exp/Cntr=0.3,0.1

Type RM Length L Ch R = 1,12514,438,438,438
BEGIN DESCRIPTION:
Stream0262 26.0
END DESCRIPTION:
XS GIS Cut Line= 3
      1820374.99     13909525.00      1819975.00     13909425.00
      1819626.46     13909243.86
#Sta/Elev= 30
  4591.3 2088.58  4684.1 2081.47  4691.8 2080.14  4733.0 2076.95  4756.2 2074.01
  4807.8 2071.35  4820.6 2069.40  4838.7 2067.72  4855.9 2067.57  4869.6 2068.13
  4879.9 2067.77  4903.1 2065.29  4944.3 2062.90  4996.3 2062.04  4996.8 2061.54
  5005.3 2061.54  5005.8 2062.04  5012.2 2062.41  5026.1 2067.02  5034.0 2070.39
  5048.7 2074.71  5071.2 2079.10  5122.4 2084.11  5183.1 2088.07  5210.9 2090.76
  5240.3 2094.91  5330.4 2101.62  5337.9 2102.88  5375.5 2105.88  5396.4 2108.87
#Mann=5,-1,0
  4591.3     0.1       0  4855.9    0.07       0  4996.3    0.05       0
  5005.8    0.07       0  5012.2     0.1       0
Bank Sta=4996.3,5005.8
Exp/Cntr=0.3,0.1

Type RM Length L Ch R = 1,12076,428,428,428
BEGIN DESCRIPTION:
Stream0262 25.0
END DESCRIPTION:
XS GIS Cut Line= 3
      1820613.67     13909439.71      1820275.00     13909125.00
      1819875.01     13908825.01
#Sta/Elev= 30
  4537.7 2113.86  4568.3 2109.17  4604.0 2105.90  4731.0 2090.00  4759.4 2088.12
  4787.7 2084.52  4837.1 2080.81  4858.6 2078.09  4879.6 2077.20  4907.9 2073.71
  4922.1 2071.22  4936.2 2065.91  4943.6 2060.22  4959.8 2055.78  4960.3 2055.28
  4969.4 2055.78  4986.1 2057.53  5007.3 2057.59  5036.5 2061.49  5050.0 2065.26
  5071.9 2068.68  5128.1 2072.53  5192.7 2080.83  5213.6 2082.16  5250.0 2088.83
  5300.0 2094.20  5378.1 2108.76  5436.5 2116.23  5463.6 2121.44  5500.0 2124.96
#Mann=3,-1,0
  4537.7     0.1       0  4959.8    0.05       0  4969.4     0.1       0
Bank Sta=4959.8,4969.4
Exp/Cntr=0.3,0.1

Type RM Length L Ch R = 1,11648,474,474,474
BEGIN DESCRIPTION:
Stream0262 24.0
END DESCRIPTION:
XS GIS Cut Line= 3
      1820658.87     13909080.15      1820475.00     13908775.00
      1820275.02     13908725.01
#Sta/Elev= 30
  4643.7 2080.15  4664.1 2079.72  4673.1 2078.86  4722.3 2077.72  4753.4 2076.20
  4801.9 2075.38  4833.0 2073.56  4860.2 2073.80  4883.2 2072.42  4918.4 2068.56
  4928.1 2068.15  4949.5 2064.39  4955.3 2059.92  4987.4 2052.88  4987.9 2052.38
  4996.5 2052.38  4997.0 2052.88  5023.2 2053.82  5030.9 2055.54  5051.5 2057.28
  5072.1 2058.30  5082.4 2057.70  5092.7 2058.59  5105.6 2062.35  5113.4 2066.03
  5134.0 2071.40  5141.7 2074.70  5154.6 2078.04  5164.9 2079.71  5206.1 2084.52
#Mann=3,-1,0
  4643.7     0.1       0  4987.4    0.05       0  4997.0     0.1       0
Bank Sta=4987.4,4997
Exp/Cntr=0.3,0.1

Type RM Length L Ch R = 1,11174,847,847,847
BEGIN DESCRIPTION:
Stream0262 23.0
END DESCRIPTION:
XS GIS Cut Line= 3
      1820766.91     13909145.78      1820675.00     13908375.00
      1820333.97     13908211.58
#Sta/Elev= 30
  4223.5 2083.26  4224.1 2083.26  4314.9 2078.97  4516.3 2073.75  4538.4 2073.86
  4566.7 2071.26  4667.4 2065.59  4790.9 2063.88  4848.7 2059.04  4878.9 2054.82
  4929.2 2053.94  4949.4 2055.01  4961.0 2053.46  4969.5 2051.10  4992.4 2049.75
  4992.9 2049.25  5002.0 2049.75  5013.8 2050.17  5021.9 2052.69  5031.0 2056.30
  5036.5 2060.49  5053.6 2069.09  5059.2 2072.93  5066.3 2074.11  5110.6 2076.97
  5210.4 2079.43  5240.4 2081.87  5314.0 2081.87  5376.3 2083.64  5377.9 2083.64
#Mann=5,-1,0
  4223.5    0.07       0  4224.1     0.1       0  4992.4    0.05       0
  5002.0     0.1       0  5376.3    0.07       0
Bank Sta=4992.4,5002
Exp/Cntr=0.3,0.1

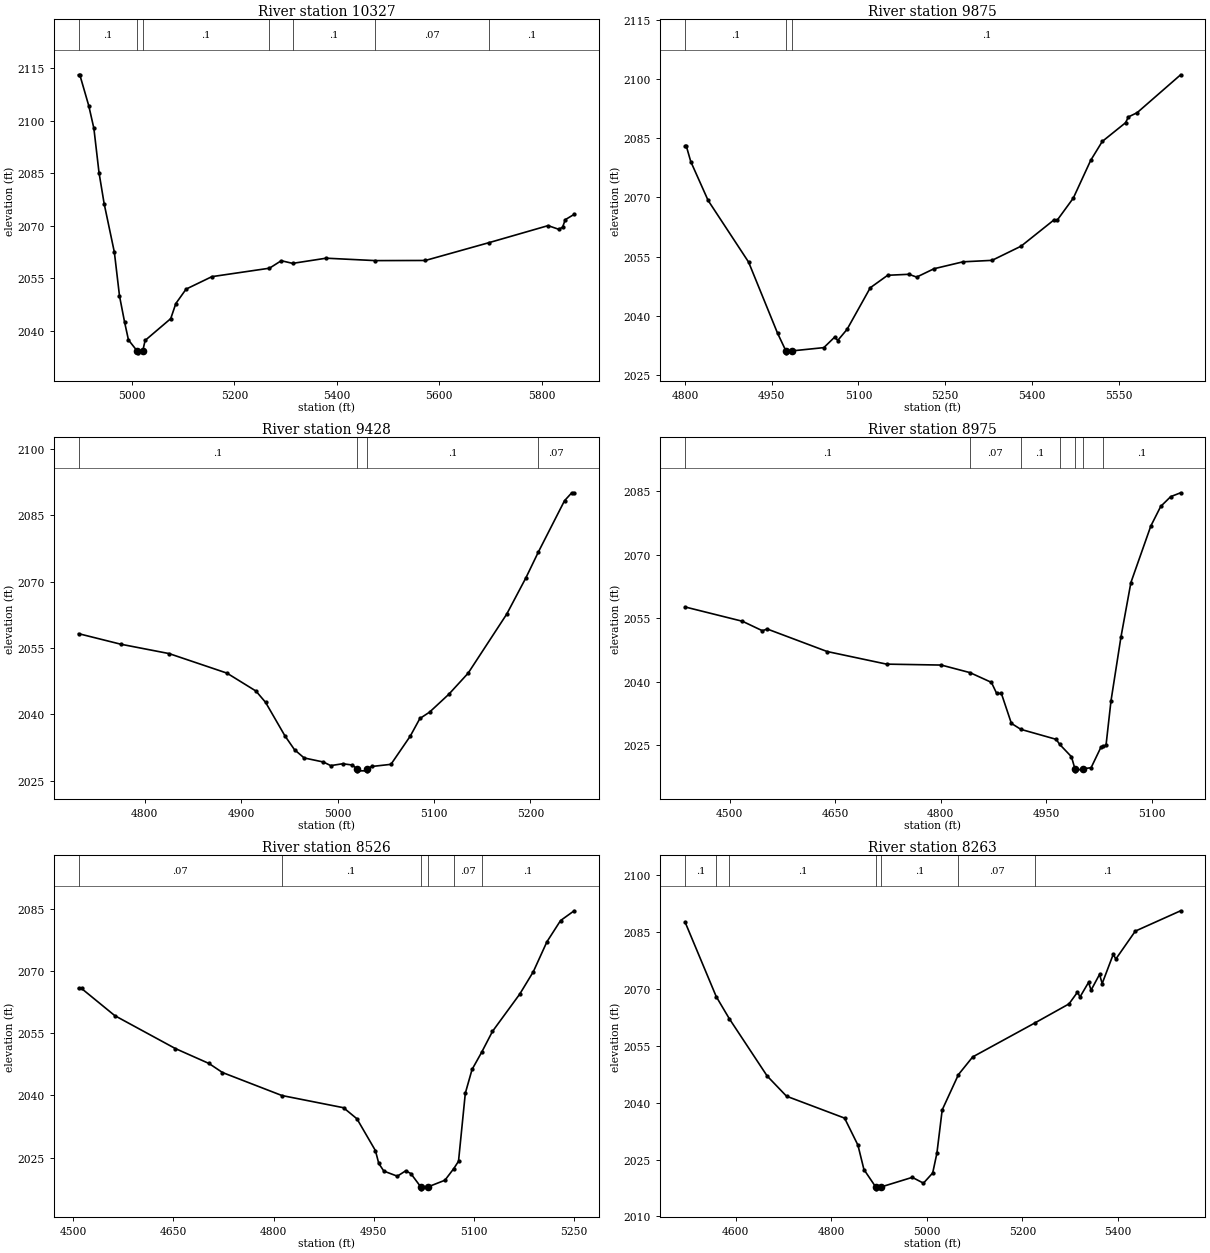
Type RM Length L Ch R = 1,10327,452,452,452
BEGIN DESCRIPTION:
Stream0262 22.0
END DESCRIPTION:
XS GIS Cut Line= 4
      1821425.00     13907925.00      1821325.00     13907925.00
      1821175.00     13907925.00      1820486.14     13908125.69
#Sta/Elev= 30
  4895.8 2113.12  4898.3 2113.12  4915.8 2104.28  4925.8 2097.82  4935.8 2085.20
  4945.8 2076.34  4965.8 2062.43  4975.8 2049.97  4985.8 2042.44  4993.3 2037.39
  5010.5 2034.21  5011.0 2033.71  5021.1 2034.21  5025.8 2037.25  5075.8 2043.48
  5085.8 2047.80  5105.8 2051.91  5156.2 2055.47  5268.5 2057.88  5291.6 2060.02
  5313.7 2059.26  5379.2 2060.74  5475.2 2060.05  5572.8 2060.09  5697.6 2065.20
  5812.4 2070.04  5833.2 2068.99  5840.7 2069.59  5845.9 2071.74  5863.3 2073.26
#Mann=7,-1,0
  4895.8     0.1       0  5010.5    0.05       0  5021.1     0.1       0
  5268.5    0.07       0  5313.7     0.1       0  5475.2    0.07       0
  5697.6     0.1       0
Bank Sta=5010.5,5021.1
Exp/Cntr=0.3,0.1

Type RM Length L Ch R = 1,9875,447,447,447
BEGIN DESCRIPTION:
Stream0262 21.0
END DESCRIPTION:
XS GIS Cut Line= 3
      1821275.00     13907575.00      1821075.00     13907575.00
      1820419.97     13907522.85
#Sta/Elev= 30
  4800.0 2082.88  4802.5 2082.88  4810.0 2079.05  4840.0 2069.21  4910.0 2053.60
  4960.0 2035.62  4974.5 2031.12  4975.0 2030.62  4985.5 2031.12  5040.1 2031.94
  5059.1 2034.64  5064.1 2033.74  5080.3 2036.57  5120.4 2047.10  5150.5 2050.26
  5187.3 2050.51  5200.6 2049.80  5230.7 2051.92  5280.9 2053.67  5331.0 2054.04
  5381.2 2057.63  5438.7 2064.35  5443.7 2064.22  5471.5 2069.80  5501.6 2079.37
  5521.6 2084.15  5561.8 2088.88  5566.9 2090.37  5581.8 2091.42  5657.1 2101.03
#Mann=3,-1,0
  4800.0     0.1       0  4974.5    0.05       0  4985.5     0.1       0
Bank Sta=4974.5,4985.5
Exp/Cntr=0.3,0.1

Type RM Length L Ch R = 1,9428,453,453,453
BEGIN DESCRIPTION:
Stream0262 20.0
END DESCRIPTION:
XS GIS Cut Line= 3
      1821088.94     13907227.26      1820825.00     13907225.00
      1820574.95     13907225.00
#Sta/Elev= 30
  4731.3 2058.23  4775.2 2055.84  4825.2 2053.73  4885.2 2049.32  4915.3 2045.27
  4925.3 2042.71  4945.3 2035.17  4955.3 2032.02  4965.3 2030.16  4985.3 2029.24
  4992.8 2028.43  5005.3 2028.85  5015.3 2028.56  5019.7 2027.75  5020.2 2027.25
  5030.3 2027.25  5030.8 2027.75  5035.3 2028.23  5055.3 2028.72  5075.3 2035.08
  5085.3 2039.07  5095.3 2040.50  5115.3 2044.54  5135.3 2049.29  5175.3 2062.62
  5195.3 2070.86  5208.2 2076.68  5235.3 2088.25  5242.8 2090.04  5245.3 2090.04
#Mann=4,-1,0
  4731.3     0.1       0  5019.7    0.05       0  5030.8     0.1       0
  5208.2    0.07       0
Bank Sta=5019.7,5030.8
Exp/Cntr=0.3,0.1

Type RM Length L Ch R = 1,8975,449,449,449
BEGIN DESCRIPTION:
Stream0262 19.0
END DESCRIPTION:
XS GIS Cut Line= 3
      1821097.84     13907196.98      1820675.00     13906825.00
      1820575.00     13906725.00
#Sta/Elev= 30
  4436.7 2057.68  4518.4 2054.29  4546.8 2052.05  4553.5 2052.47  4638.8 2047.14
  4723.3 2044.16  4801.1 2043.94  4841.9 2042.15  4872.3 2039.85  4879.8 2037.22
  4886.5 2037.22  4900.7 2030.16  4914.1 2028.75  4964.3 2026.39  4969.5 2025.17
  4986.1 2022.27  4991.0 2019.44  4991.5 2018.94  5002.1 2019.44  5014.0 2019.67
  5028.2 2024.59  5031.1 2024.73  5035.2 2024.93  5042.3 2035.47  5056.4 2050.50
  5070.6 2063.44  5098.9 2076.80  5113.0 2081.44  5127.2 2083.75  5141.3 2084.66
#Mann=7,-1,0
  4436.7     0.1       0  4841.9    0.07       0  4914.1     0.1       0
  4969.5    0.07       0  4991.0    0.05       0  5002.1    0.07       0
  5031.1     0.1       0
Bank Sta=4991,5002.1
Exp/Cntr=0.3,0.1

Type RM Length L Ch R = 1,8526,263,263,263
BEGIN DESCRIPTION:
Stream0262 18.0
END DESCRIPTION:
XS GIS Cut Line= 3
      1821409.01     13906535.41      1820925.00     13906475.00
      1820675.02     13906425.00
#Sta/Elev= 30
  4507.8 2065.80  4512.3 2065.80  4562.2 2059.24  4652.9 2051.31  4703.3 2047.71
  4723.5 2045.53  4812.6 2039.98  4904.9 2037.04  4925.0 2034.37  4952.7 2026.70
  4957.7 2023.61  4965.3 2021.76  4985.5 2020.53  4998.1 2021.83  5005.8 2021.16
  5020.5 2017.98  5021.0 2017.48  5031.9 2017.98  5056.8 2019.55  5070.1 2022.36
  5077.2 2024.13  5087.4 2040.54  5097.5 2046.27  5111.8 2050.39  5128.1 2055.45
  5168.9 2064.43  5189.3 2069.84  5209.7 2077.06  5230.1 2082.17  5250.5 2084.53
#Mann=6,-1,0
  4507.8    0.07       0  4812.6     0.1       0  5020.5    0.05       0
  5031.9     0.1       0  5070.1    0.07       0  5111.8     0.1       0
Bank Sta=5020.5,5031.9
Exp/Cntr=0.3,0.1

Type RM Length L Ch R = 1,8263,573,573,573
BEGIN DESCRIPTION:
Stream0262 17.0
END DESCRIPTION:
XS GIS Cut Line= 3
      1821524.97     13906325.00      1821016.08     13906247.29
      1820540.44     13906032.44
#Sta/Elev= 30
  4494.2 2087.73  4559.6 2067.99  4587.1 2062.13  4666.1 2047.04  4706.6 2041.71
  4828.0 2035.93  4855.9 2028.81  4868.5 2022.36  4893.1 2017.76  4893.6 2017.26
  4904.5 2017.76  4969.6 2020.29  4993.0 2018.76  5012.3 2021.44  5021.1 2026.65
  5032.2 2038.10  5066.2 2047.42  5096.0 2052.08  5226.1 2061.05  5297.4 2066.07
  5315.1 2069.16  5320.5 2067.92  5338.2 2071.73  5343.7 2069.73  5361.3 2073.86
  5366.8 2071.44  5389.9 2079.14  5395.4 2077.92  5436.1 2085.28  5530.9 2090.65
#Mann=7,-1,0
  4494.2     0.1       0  4559.6    0.07       0  4587.1     0.1       0
  4893.1    0.05       0  4904.5     0.1       0  5066.2    0.07       0
  5226.1     0.1       0
Bank Sta=4893.1,4904.5
Exp/Cntr=0.3,0.1

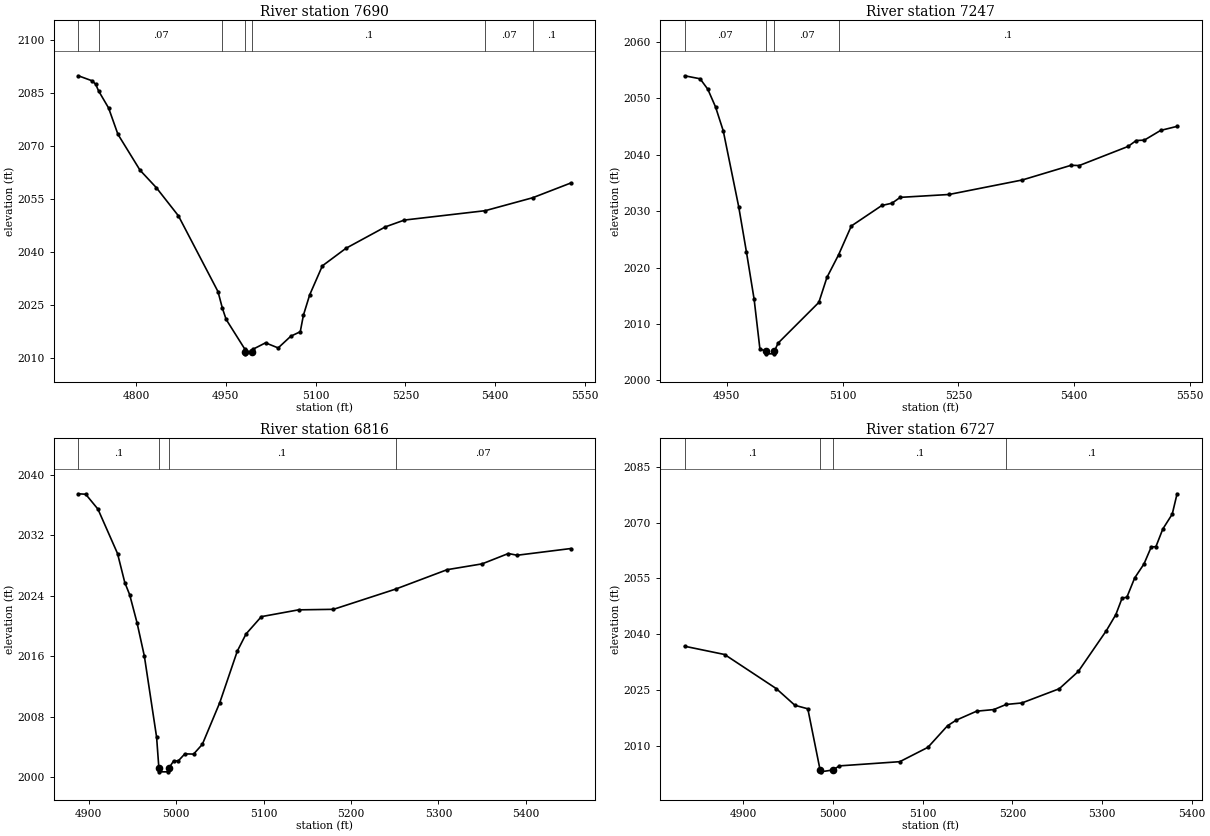
Type RM Length L Ch R = 1,7690,443,443,443
BEGIN DESCRIPTION:
Stream0262 16.0
END DESCRIPTION:
XS GIS Cut Line= 4
      1821624.99     13906074.99      1821375.00     13905925.00
      1821225.00     13905875.00      1820871.38     13905757.13
#Sta/Elev= 30
  4703.9 2089.88  4727.2 2088.44  4733.0 2087.44  4737.7 2085.60  4754.4 2080.78
  4770.0 2073.34  4806.9 2063.20  4834.1 2058.27  4871.0 2050.31  4937.1 2028.90
  4944.4 2024.23  4950.7 2021.04  4981.8 2012.68  4981.9 2011.81  4982.4 2011.31
  4993.4 2011.81  4995.4 2012.60  5016.5 2014.42  5037.6 2012.98  5058.7 2016.29
  5074.5 2017.56  5079.8 2022.25  5090.3 2028.00  5111.4 2036.17  5150.9 2041.14
  5216.8 2047.20  5248.4 2049.11  5383.4 2051.76  5462.7 2055.42  5526.3 2059.58
#Mann=7,-1,0
  4703.9     0.1       0  4737.7    0.07       0  4944.4     0.1       0
  4981.9    0.05       0  4993.4     0.1       0  5383.4    0.07       0
  5462.7     0.1       0
Bank Sta=4981.9,4993.4
Exp/Cntr=0.3,0.1

Type RM Length L Ch R = 1,7247,431,431,431
BEGIN DESCRIPTION:
Stream0262 15.0
END DESCRIPTION:
XS GIS Cut Line= 4
      1821724.97     13905575.00      1821625.00     13905575.00
      1821475.00     13905525.00      1821114.77     13905404.92
#Sta/Elev= 30
  4895.5 2053.97  4915.5 2053.44  4925.5 2051.59  4935.5 2048.46  4945.5 2044.22
  4965.5 2030.79  4975.5 2022.79  4985.5 2014.38  4993.0 2005.57  5000.3 2005.21
  5000.8 2004.71  5011.3 2004.71  5011.8 2005.21  5016.6 2006.62  5069.3 2013.82
  5079.8 2018.25  5094.8 2022.23  5111.4 2027.36  5150.9 2030.99  5164.1 2031.40
  5174.7 2032.43  5237.9 2032.94  5332.8 2035.51  5396.0 2038.11  5406.6 2038.07
  5469.8 2041.45  5480.4 2042.50  5490.9 2042.57  5512.0 2044.29  5533.3 2045.01
#Mann=4,-1,0
  4895.5    0.07       0  5000.3    0.05       0  5011.8    0.07       0
  5094.8     0.1       0
Bank Sta=5000.3,5011.8
Exp/Cntr=0.3,0.1

Type RM Length L Ch R = 1,6816,89,89,89
BEGIN DESCRIPTION:
Stream0262 14.0
END DESCRIPTION:
XS GIS Cut Line= 4
      1821825.04     13905225.02      1821725.00     13905175.00
      1821625.00     13905175.00      1821273.64     13905175.00
#Sta/Elev= 30
  4888.2 2037.50  4896.6 2037.44  4910.6 2035.47  4933.0 2029.59  4941.3 2025.75
  4946.9 2024.13  4955.3 2020.43  4963.7 2016.00  4977.7 2005.27  4980.3 2001.18
  4980.8 2000.68  4991.3 2000.68  4991.8 2001.18  4997.2 2002.13  5002.5 2002.13
  5010.0 2003.06  5020.0 2003.03  5030.0 2004.32  5050.0 2009.86  5070.0 2016.67
  5080.0 2018.94  5097.5 2021.23  5140.0 2022.13  5180.0 2022.20  5251.1 2024.88
  5310.0 2027.45  5350.0 2028.22  5380.0 2029.59  5390.0 2029.36  5451.4 2030.25
#Mann=4,-1,0
  4888.2     0.1       0  4980.3    0.05       0  4991.8     0.1       0
  5251.1    0.07       0
Bank Sta=4980.3,4991.8
Exp/Cntr=0.3,0.1

Type RM Length L Ch R = 1,6727,366,366,366
BEGIN DESCRIPTION:
Stream0262 13.1
END DESCRIPTION:
XS GIS Cut Line= 3
      1821856.52     13905226.55      1821722.40     13905059.88
      1821622.22     13904739.83
#Sta/Elev= 30
  4834.4 2036.75  4879.0 2034.53  4936.6 2025.37  4957.4 2020.88  4971.8 2019.94
  4985.5 2003.50  4986.0 2003.00  4999.8 2003.50  5007.0 2004.60  5074.4 2005.73
  5105.8 2009.59  5127.7 2015.40  5137.3 2016.88  5160.1 2019.30  5179.2 2019.73
  5193.1 2021.11  5210.6 2021.51  5252.3 2025.33  5273.5 2029.97  5304.9 2040.97
  5315.4 2045.26  5322.4 2049.69  5327.7 2049.92  5336.4 2055.10  5346.8 2058.87
  5354.9 2063.44  5360.1 2063.51  5367.8 2068.26  5378.3 2072.25  5383.7 2077.72
#Mann=4,-1,0
  4834.4     0.1       0  4985.5    0.05       0  4999.8     0.1       0
  5193.1     0.1       0
Bank Sta=4985.5,4999.8
Exp/Cntr=0.3,0.1