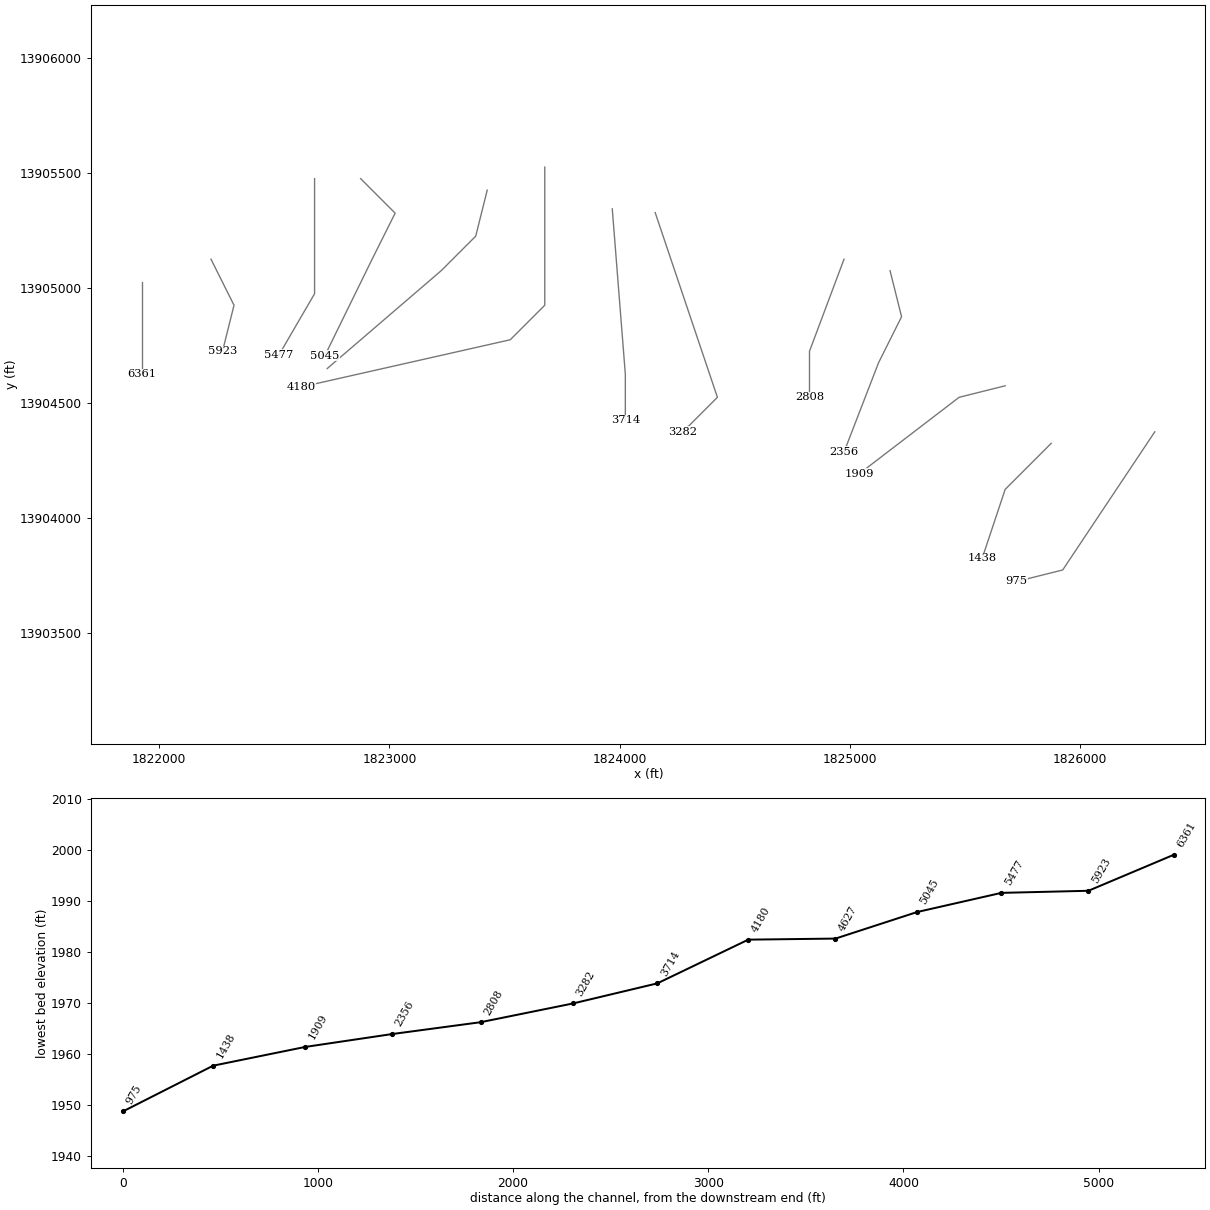
HEC-RAS study Stream0262.prj: Stream0262 Base Level Engineering

--- Stream0262.g01 (geometry) --- (continued)

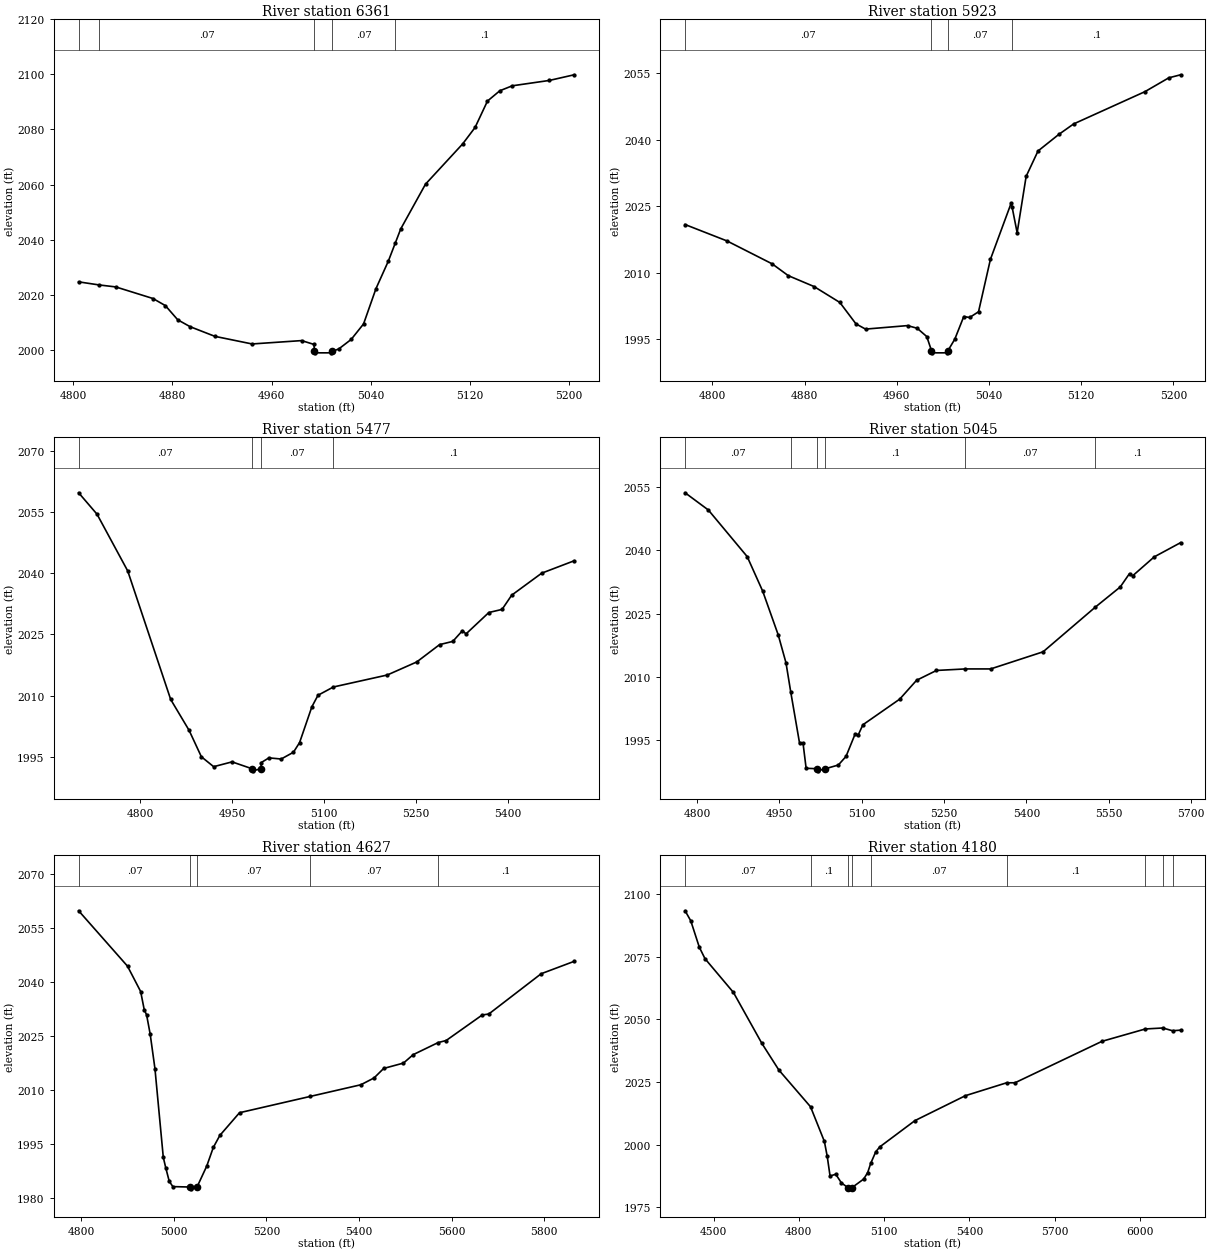
Type RM Length L Ch R = 1,6361,438,438,438
BEGIN DESCRIPTION:
Stream0262 13.0
END DESCRIPTION:
XS GIS Cut Line= 3
      1821925.00     13905024.95      1821925.00     13904825.00
      1821925.00     13904624.95
#Sta/Elev= 30
  4804.3 2024.75  4821.0 2023.62  4834.3 2022.91  4864.3 2018.71  4874.3 2016.14
  4884.3 2010.99  4894.3 2008.49  4914.3 2004.99  4944.3 2002.23  4984.3 2003.45
  4994.3 2002.06  4994.6 1999.51  4995.1 1999.01  5008.4 1999.01  5008.9 1999.51
  5014.3 2000.43  5024.3 2003.87  5034.3 2009.50  5044.3 2022.28  5054.3 2032.28
  5059.8 2038.70  5064.3 2043.95  5084.3 2060.18  5114.3 2074.78  5124.3 2080.73
  5134.3 2090.30  5144.3 2094.05  5154.3 2095.84  5184.3 2097.79  5204.3 2099.84
#Mann=5,-1,0
  4804.3     0.1       0  4821.0    0.07       0  4994.6    0.05       0
  5008.9    0.07       0  5059.8     0.1       0
Bank Sta=4994.6,5008.9
Exp/Cntr=0.3,0.1

Type RM Length L Ch R = 1,5923,446,446,446
BEGIN DESCRIPTION:
Stream0262 12.0
END DESCRIPTION:
XS GIS Cut Line= 3
      1822225.00     13905125.01      1822325.00     13904925.00
      1822274.99     13904724.97
#Sta/Elev= 30
  4776.4 2020.88  4812.7 2017.19  4851.9 2012.02  4865.9 2009.36  4888.2 2006.91
  4910.6 2003.32  4924.6 1998.49  4932.9 1997.31  4969.3 1998.10  4977.7 1997.50
  4986.0 1995.63  4990.1 1992.46  4990.6 1991.96  5003.9 1991.96  5004.4 1992.46
  5010.3 1995.03  5018.1 2000.14  5023.2 1999.93  5030.9 2001.22  5041.2 2013.02
  5059.3 2025.77  5060.0 2024.85  5064.4 2019.04  5072.2 2031.74  5082.5 2037.46
  5100.5 2041.19  5113.4 2043.56  5175.2 2050.83  5195.9 2053.95  5206.2 2054.64
#Mann=4,-1,0
  4776.4    0.07       0  4990.1    0.05       0  5004.4    0.07       0
  5060.0     0.1       0
Bank Sta=4990.1,5004.4
Exp/Cntr=0.3,0.1

Type RM Length L Ch R = 1,5477,432,432,432
BEGIN DESCRIPTION:
Stream0262 11.0
END DESCRIPTION:
XS GIS Cut Line= 4
      1822675.00     13905475.01      1822675.00     13905175.00
      1822675.00     13904975.00      1822520.41     13904709.31
#Sta/Elev= 30
  4700.0 2059.76  4730.0 2054.50  4780.0 2040.58  4850.0 2009.06  4880.0 2001.48
  4900.0 1995.00  4920.0 1992.57  4950.0 1993.75  4982.8 1992.05  4983.3 1991.55
  4997.2 1992.05  4997.5 1993.57  5010.0 1994.73  5030.0 1994.45  5050.0 1996.11
  5060.0 1998.48  5080.0 2007.25  5090.0 2010.09  5115.1 2012.12  5202.9 2015.06
  5250.9 2018.26  5288.1 2022.51  5309.6 2023.30  5325.4 2025.94  5331.2 2025.14
  5368.4 2030.39  5389.9 2031.15  5405.6 2034.64  5454.5 2040.04  5507.4 2043.08
#Mann=4,-1,0
  4700.0    0.07       0  4982.8    0.05       0  4997.2    0.07       0
  5115.1     0.1       0
Bank Sta=4982.8,4997.2
Exp/Cntr=0.3,0.1

Type RM Length L Ch R = 1,5045,418,418,418
BEGIN DESCRIPTION:
Stream0262 10.0
END DESCRIPTION:
XS GIS Cut Line= 4
      1822875.02     13905474.98      1823025.00     13905325.00
      1822925.00     13905125.00      1822719.45     13904705.57
#Sta/Elev= 30
  4778.3 2053.61  4820.7 2049.53  4891.4 2038.51  4919.7 2030.32  4948.0 2019.96
  4962.1 2013.37  4970.8 2006.43  4986.9 1994.30  4993.2 1994.30  4998.8 1988.40
  5019.5 1988.30  5020.0 1987.80  5033.9 1988.30  5057.5 1989.18  5071.5 1991.22
  5088.2 1996.56  5093.8 1996.32  5102.2 1998.70  5169.3 2004.77  5200.0 2009.23
  5236.3 2011.56  5288.8 2011.92  5335.0 2011.92  5430.5 2015.97  5525.8 2026.56
  5571.1 2031.32  5588.0 2034.50  5593.6 2033.95  5633.0 2038.44  5681.1 2041.81
#Mann=6,-1,0
  4778.3    0.07       0  4970.8     0.1       0  5019.5    0.05       0
  5033.9     0.1       0  5288.8    0.07       0  5525.8     0.1       0
Bank Sta=5019.5,5033.9
Exp/Cntr=0.3,0.1

Type RM Length L Ch R = 1,4627,447,447,447
BEGIN DESCRIPTION:
Stream0262 9.0
END DESCRIPTION:
XS GIS Cut Line= 4
      1823424.99     13905424.98      1823375.00     13905225.00
      1823225.00     13905075.00      1822730.00     13904649.97
#Sta/Elev= 30
  4794.2 2059.77  4899.8 2044.40  4928.2 2037.37  4935.9 2032.35  4941.1 2030.86
  4948.8 2025.55  4959.1 2015.96  4977.1 1991.37  4982.3 1988.52  4990.0 1984.69
  4997.8 1983.23  5035.5 1983.11  5036.0 1982.61  5050.0 1983.11  5071.0 1988.92
  5085.2 1994.10  5099.3 1997.43  5141.8 2003.73  5294.8 2008.26  5404.0 2011.49
  5432.5 2013.38  5453.3 2016.02  5496.1 2017.51  5517.0 2019.84  5571.0 2023.20
  5588.3 2023.77  5666.2 2030.85  5680.5 2031.13  5793.6 2042.30  5864.9 2045.74
#Mann=5,-1,0
  4794.2    0.07       0  5035.5    0.05       0  5050.0    0.07       0
  5294.8    0.07       0  5571.0     0.1       0
Bank Sta=5035.5,5050
Exp/Cntr=0.3,0.1

Type RM Length L Ch R = 1,4180,466,466,466
BEGIN DESCRIPTION:
Stream0262 8.0
END DESCRIPTION:
XS GIS Cut Line= 4
      1823675.00     13905524.99      1823675.00     13904925.00
      1823525.00     13904775.00      1822616.62     13904569.76
#Sta/Elev= 30
  4400.0 2093.26  4420.0 2089.25  4450.0 2078.74  4470.0 2074.16  4570.0 2060.71
  4670.0 2040.41  4730.0 2029.75  4841.3 2015.12  4890.0 2001.31  4900.0 1995.38
  4910.0 1987.52  4930.0 1988.22  4950.0 1984.76  4972.7 1982.90  4973.2 1982.40
  4987.2 1982.90  5028.3 1986.30  5042.4 1988.90  5053.2 1992.59  5070.7 1997.15
  5084.8 1999.12  5208.6 2009.60  5386.4 2019.55  5530.9 2024.67  5560.7 2024.69
  5866.6 2041.21  6019.2 2046.14  6080.7 2046.53  6114.8 2045.43  6143.4 2045.67
#Mann=9,-1,0
  4400.0    0.07       0  4841.3     0.1       0  4972.7    0.05       0
  4987.2     0.1       0  5053.2    0.07       0  5530.9     0.1       0
  6019.2    0.07       0  6080.7     0.1       0  6114.8    0.07       0
Bank Sta=4972.7,4987.2
Exp/Cntr=0.3,0.1

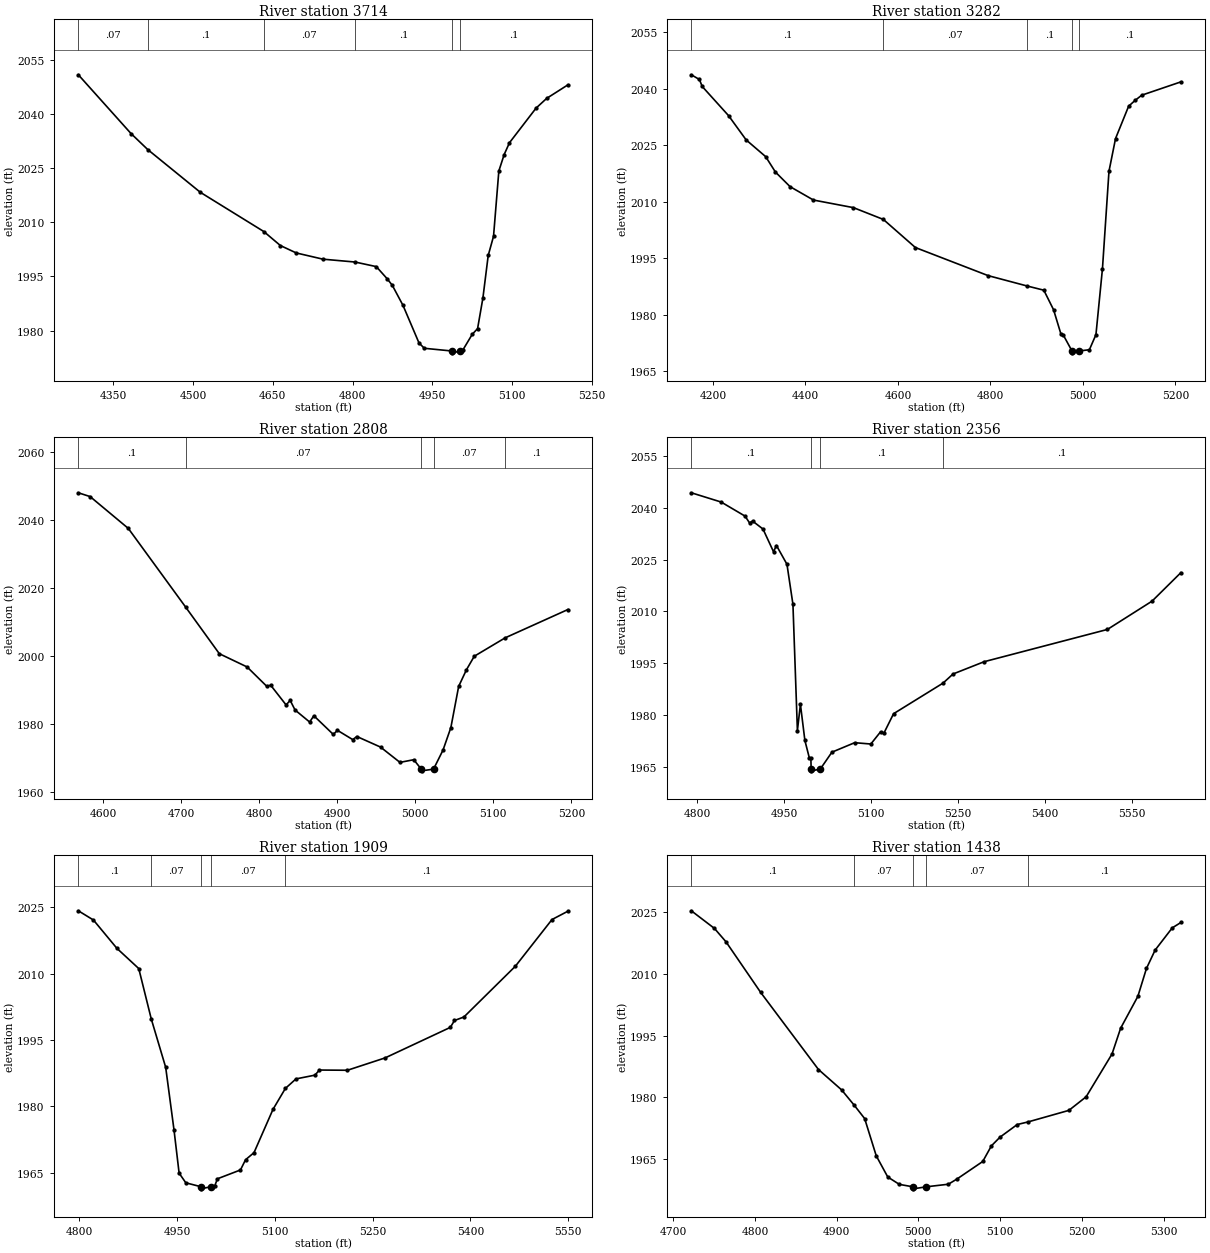
Type RM Length L Ch R = 1,3714,432,432,432
BEGIN DESCRIPTION:
Stream0262 7.0
END DESCRIPTION:
XS GIS Cut Line= 3
      1823968.21     13905343.77      1824025.00     13904625.00
      1824025.00     13904425.01
#Sta/Elev= 30
  4284.2 2050.83  4383.3 2034.56  4414.9 2030.11  4513.7 2018.29  4633.1 2007.43
  4664.2 2003.56  4694.2 2001.50  4744.4 1999.78  4804.7 1998.99  4844.7 1997.72
  4864.8 1994.41  4874.8 1992.54  4894.9 1986.99  4925.0 1976.59  4935.0 1975.11
  4987.5 1974.35  4988.0 1973.85  5002.9 1974.35  5007.7 1974.68  5025.2 1978.99
  5035.2 1980.55  5045.2 1989.02  5055.2 2000.81  5065.2 2006.11  5075.2 2024.20
  5085.2 2028.74  5095.2 2032.02  5145.2 2041.60  5165.2 2044.30  5205.2 2048.05
#Mann=6,-1,0
  4284.2    0.07       0  4414.9     0.1       0  4633.1    0.07       0
  4804.7     0.1       0  4987.5    0.05       0  5002.9     0.1       0
Bank Sta=4987.5,5002.9
Exp/Cntr=0.3,0.1

Type RM Length L Ch R = 1,3282,474,474,474
BEGIN DESCRIPTION:
Stream0262 6.0
END DESCRIPTION:
XS GIS Cut Line= 3
      1824154.69     13905327.37      1824425.00     13904525.00
      1824275.01     13904375.01
#Sta/Elev= 30
  4153.2 2043.73  4170.7 2042.48  4176.8 2040.62  4233.7 2032.89  4271.8 2026.44
  4314.0 2022.00  4335.1 2017.91  4366.7 2014.04  4417.3 2010.48  4503.9 2008.46
  4568.5 2005.33  4637.8 1997.87  4795.2 1990.41  4879.5 1987.66  4915.5 1986.55
  4936.6 1981.35  4952.6 1974.87  4957.9 1974.58  4976.4 1970.42  4976.9 1969.92
  4991.8 1970.42  5014.0 1970.74  5028.2 1974.74  5042.3 1992.26  5056.4 2018.12
  5070.6 2026.81  5098.9 2035.39  5113.0 2036.94  5127.2 2038.31  5212.0 2041.85
#Mann=5,-1,0
  4153.2     0.1       0  4568.5    0.07       0  4879.5     0.1       0
  4976.4    0.05       0  4991.8     0.1       0
Bank Sta=4976.4,4991.8
Exp/Cntr=0.3,0.1

Type RM Length L Ch R = 1,2808,452,452,452
BEGIN DESCRIPTION:
Stream0262 5.0
END DESCRIPTION:
XS GIS Cut Line= 3
      1824974.98     13905124.96      1824825.00     13904725.00
      1824825.00     13904524.96
#Sta/Elev= 30
  4568.5 2048.05  4583.6 2046.93  4632.5 2037.57  4705.9 2014.44  4749.1 2000.71
  4784.7 1996.81  4809.6 1991.18  4815.0 1991.41  4834.6 1985.65  4839.9 1986.96
  4846.1 1984.15  4864.8 1980.61  4870.2 1982.45  4895.1 1976.96  4900.4 1978.17
  4920.0 1975.44  4925.3 1976.35  4955.6 1973.24  4980.5 1968.74  4998.2 1969.52
  5007.8 1966.75  5008.3 1966.25  5023.5 1966.75  5035.7 1972.38  5045.7 1978.97
  5055.7 1991.10  5065.7 1996.00  5075.7 1999.96  5115.3 2005.38  5195.7 2013.71
#Mann=5,-1,0
  4568.5     0.1       0  4705.9    0.07       0  5007.8    0.05       0
  5023.5    0.07       0  5115.3     0.1       0
Bank Sta=5007.8,5023.5
Exp/Cntr=0.3,0.1

Type RM Length L Ch R = 1,2356,447,447,447
BEGIN DESCRIPTION:
Stream0262 4.0
END DESCRIPTION:
XS GIS Cut Line= 4
      1825175.01     13905074.95      1825225.00     13904875.00
      1825125.00     13904675.00      1824975.53     13904288.51
#Sta/Elev= 30
  4790.1 2044.28  4841.6 2041.60  4882.8 2037.53  4890.6 2035.55  4895.7 2036.11
  4913.7 2033.80  4931.8 2027.25  4936.9 2029.04  4955.0 2023.62  4965.3 2012.05
  4973.0 1975.59  4978.2 1983.16  4985.9 1972.71  4993.6 1967.65  4996.2 1967.65
  4996.7 1964.44  4997.2 1963.94  5012.4 1964.44  5032.5 1969.33  5071.7 1972.07
  5099.6 1971.69  5116.4 1975.22  5122.0 1974.79  5138.8 1980.45  5224.1 1989.29
  5241.3 1991.92  5294.9 1995.47  5507.4 2004.79  5584.4 2012.97  5634.2 2021.22
#Mann=4,-1,0
  4790.1     0.1       0  4996.7    0.05       0  5012.4     0.1       0
  5224.1     0.1       0
Bank Sta=4996.7,5012.4
Exp/Cntr=0.3,0.1

Type RM Length L Ch R = 1,1909,471,471,471
BEGIN DESCRIPTION:
Stream0262 3.0
END DESCRIPTION:
XS GIS Cut Line= 3
      1825674.96     13904574.99      1825475.00     13904525.00
      1825042.21     13904193.78
#Sta/Elev= 30
  4798.5 2024.16  4821.7 2022.07  4857.7 2015.68  4891.2 2011.12  4910.4 1999.74
  4932.5 1988.83  4945.3 1974.67  4953.1 1964.95  4963.4 1962.77  4986.0 1961.91
  4986.5 1961.41  5002.6 1961.91  5007.8 1962.10  5011.9 1963.68  5047.2 1965.67
  5055.0 1967.97  5068.0 1969.58  5097.1 1979.34  5116.1 1984.07  5132.4 1986.22
  5161.5 1987.07  5168.3 1988.22  5211.3 1988.17  5269.1 1990.96  5369.2 1997.85
  5375.5 1999.40  5390.0 2000.19  5468.9 2011.64  5525.1 2022.18  5549.6 2024.07
#Mann=5,-1,0
  4798.5     0.1       0  4910.4    0.07       0  4986.0    0.05       0
  5002.6    0.07       0  5116.1     0.1       0
Bank Sta=4986,5002.6
Exp/Cntr=0.3,0.1

Type RM Length L Ch R = 1,1438,463,463,463
BEGIN DESCRIPTION:
Stream0262 2.0
END DESCRIPTION:
XS GIS Cut Line= 3
      1825875.01     13904325.01      1825675.00     13904125.00
      1825574.99     13903824.98
#Sta/Elev= 30
  4722.2 2025.33  4750.5 2021.04  4764.6 2017.80  4807.1 2005.48  4877.8 1986.75
  4906.1 1981.80  4921.5 1978.08  4934.3 1974.83  4948.5 1965.77  4962.6 1960.62
  4976.8 1958.83  4993.2 1958.25  4993.7 1957.75  5009.9 1958.25  5036.7 1958.87
  5047.2 1960.13  5078.8 1964.40  5089.4 1968.20  5099.9 1970.31  5121.0 1973.38
  5134.0 1974.00  5184.2 1976.82  5205.3 1980.12  5237.0 1990.53  5247.5 1996.78
  5268.6 2004.53  5279.1 2011.31  5289.7 2015.77  5310.7 2021.18  5321.3 2022.49
#Mann=5,-1,0
  4722.2     0.1       0  4921.5    0.07       0  4993.2    0.05       0
  5009.9    0.07       0  5134.0     0.1       0
Bank Sta=4993.2,5009.9
Exp/Cntr=0.3,0.1

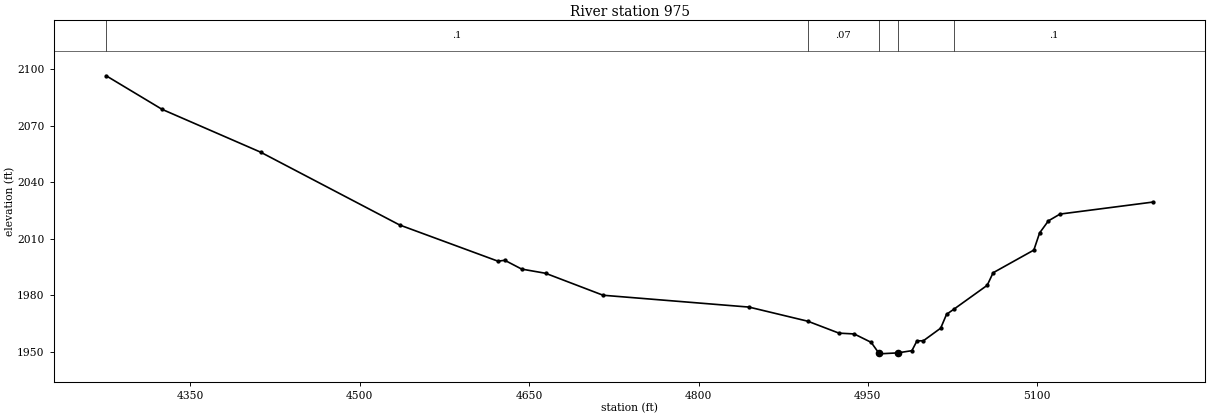
Type RM Length L Ch R = 1,975,0,0,0
BEGIN DESCRIPTION:
Stream0262 1.0
END DESCRIPTION:
XS GIS Cut Line= 3
      1826324.98     13904374.97      1825925.00     13903775.00
      1825725.03     13903725.01
#Sta/Elev= 30
  4275.4 2096.57  4324.9 2078.73  4412.1 2055.99  4535.3 2017.27  4622.4 1998.03
  4628.4 1998.51  4643.4 1993.83  4664.5 1991.61  4715.5 1979.93  4844.7 1973.64
  4896.9 1966.11  4924.4 1959.79  4937.9 1959.36  4952.9 1954.90  4959.6 1949.29
  4960.1 1948.79  4976.3 1949.29  4989.0 1950.47  4993.5 1955.71  4999.1 1955.71
  5014.5 1962.44  5019.7 1969.81  5025.9 1972.39  5055.7 1985.21  5060.9 1991.87
  5097.0 2003.94  5102.1 2013.04  5109.9 2019.47  5120.2 2023.07  5202.6 2029.46
#Mann=5,-1,0
  4275.4     0.1       0  4896.9    0.07       0  4959.6    0.05       0
  4976.3    0.07       0  5025.9     0.1       0
Bank Sta=4959.6,4976.3
Exp/Cntr=0.3,0.1

Chan Stop Cuts=-1