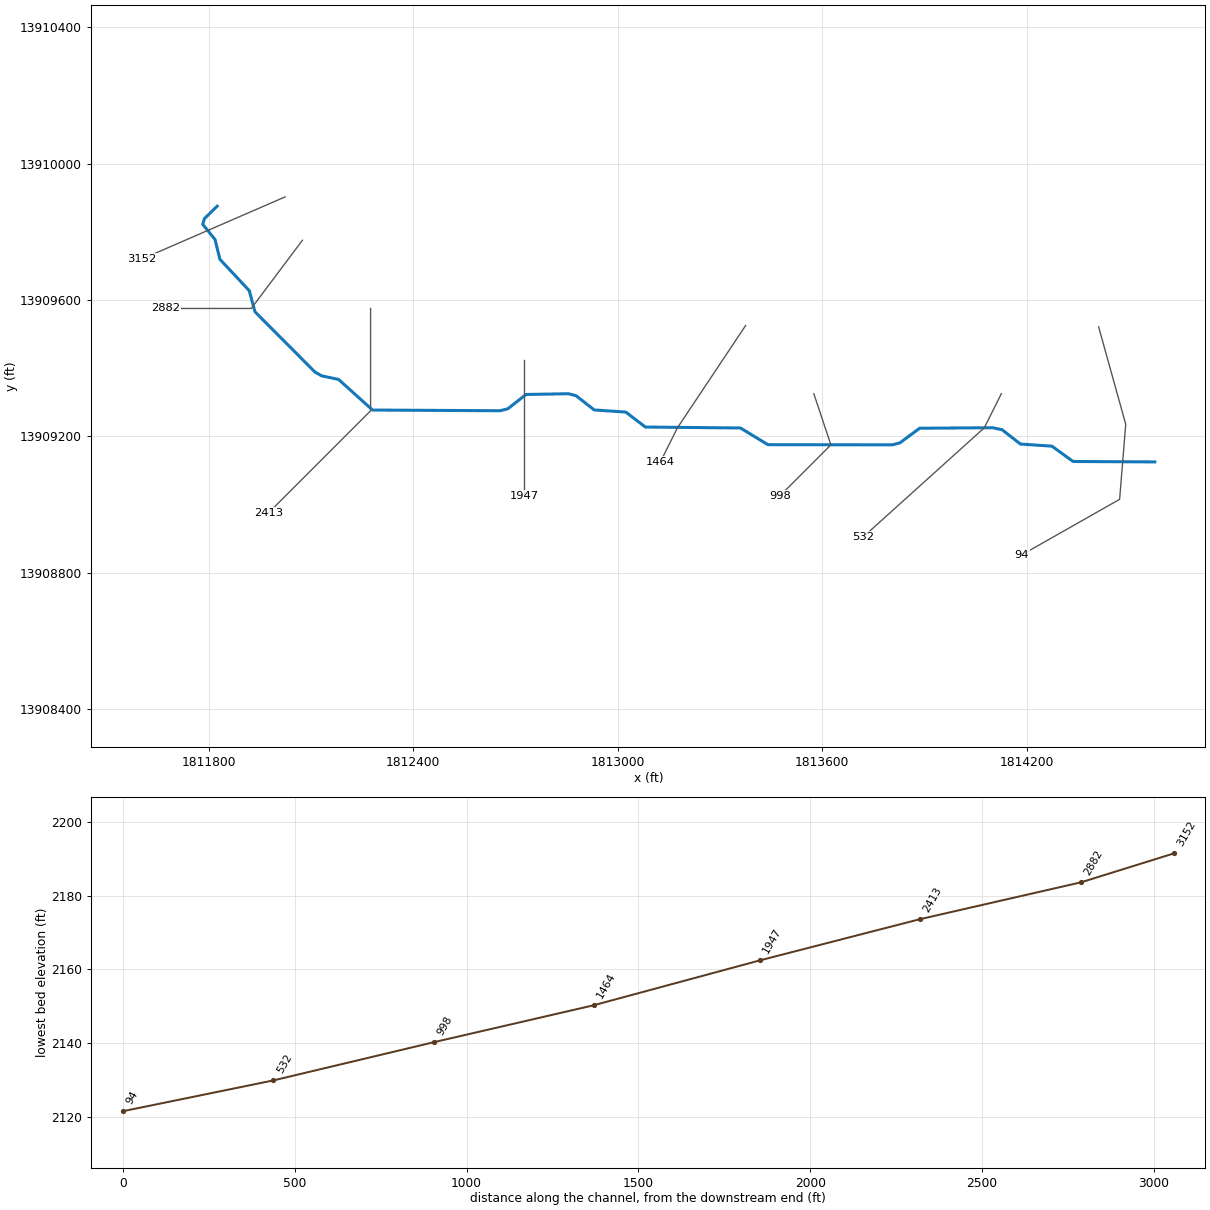
--- Stream0263.prj (project) ---

Proj Title=Stream0263 Base Level Engineering
Current Plan=p01
Default Exp/Contr=0.3,0.1
English Units
Geom File=g01
Flow File=f01
Plan File=p01
Y Axis Title=Elevation
X Axis Title(PF)=Main Channel Distance
X Axis Title(XS)=Station
BEGIN DESCRIPTION:
Stream0263
END DESCRIPTION:
DSS Export Rating Curves= 0
DSS Export Rating Curve Sorted= 0
DSS Export Volume Flow Curves= 0
DXF OffsetX= 0
DXF OffsetY= 0
DXF ScaleX= 1
DXF ScaleY= 10

--- Stream0263.p01 (plan) ---

Plan Title=Multiple Run
Short Identifier=Multiple
Geom File=g01
Flow File=f01
Subcritical Flow
K Sum by GR= 0
Std Step Tol= 0.01
Critical Tol= 0.01
Num of Std Step Trials= 20
Max Error Tol= 0.3
Flow Tol Ratio= 0.001
Split Flow NTrial= 30
Split Flow Tol= 0.02
Split Flow Ratio= 0.02
Log Output Level= 0
Friction Slope Method= 1
Unsteady Friction Slope Method= 2
Unsteady Bridges Friction Slope Method= 1
Parabolic Critical Depth
Global Vel Dist=  1 , 1 , 1
Global Log Level= 0
CheckData=True
Encroach Param= -1, 0, 0, 0
BEGIN DESCRIPTION:
Multiple Run
END DESCRIPTION:

--- Stream0263.f01 (steady flow) ---

Flow Title=Multiple
Program Version=4.10
Number of Profiles= 7
Profile Names=10-year,25-year,50-year,1pct_min,100-year,1pct_plu,500-year
River Rch & RM=Stream0263,Reach-1         ,3152
     631    1052    1446     962    1920    3831    3344
Boundary for River Rch & Prof#=Stream0263,Reach-1         , 1
Up Type= 0
Dn Type= 3
Dn Slope=0.01
Boundary for River Rch & Prof#=Stream0263,Reach-1         , 2
Up Type= 0
Dn Type= 3
Dn Slope=0.01
Boundary for River Rch & Prof#=Stream0263,Reach-1         , 3
Up Type= 0
Dn Type= 3
Dn Slope=0.01
Boundary for River Rch & Prof#=Stream0263,Reach-1         , 4
Up Type= 0
Dn Type= 3
Dn Slope=0.01
Boundary for River Rch & Prof#=Stream0263,Reach-1         , 5
Up Type= 0
Dn Type= 3
Dn Slope=0.01
Boundary for River Rch & Prof#=Stream0263,Reach-1         , 6
Up Type= 0
Dn Type= 3
Dn Slope=0.01
Boundary for River Rch & Prof#=Stream0263,Reach-1         , 7
Up Type= 0
Dn Type= 3
Dn Slope=0.01
DSS Import GetInterval= 0
DSS Import GetPeak= 0
DSS Import FillOption= 0

--- Stream0263.g01 (geometry) ---

Geom Title=Existing Conditions
Program Version=4.10

River Reach=Stream0263      ,Reach-1
Reach XY= 30
        1811825.       13909875.      1811787.67      13909838.4
      1811782.58      13909821.8      1811818.71     13909777.31
      1811833.13     13909718.96      1811919.13     13909627.28
      1811935.78     13909565.32      1812111.79     13909388.63
      1812131.05     13909377.53      1812181.04     13909366.82
      1812280.86     13909277.06      1812654.97     13909275.07
      1812677.33     13909280.75      1812730.94     13909322.75
      1812854.96     13909324.95      1812877.33     13909319.26
      1812930.98     13909277.36       1813023.4     13909271.14
      1813080.94     13909227.26      1813359.78     13909224.48
      1813440.22     13909175.52      1813804.97     13909175.07
      1813827.33     13909180.75       1813885.5     13909223.78
      1814100.08      13909225.2      1814127.34     13909219.26
      1814180.98     13909177.36       1814273.4     13909171.14
       1814335.5     13909126.22        1814575.       13909125.

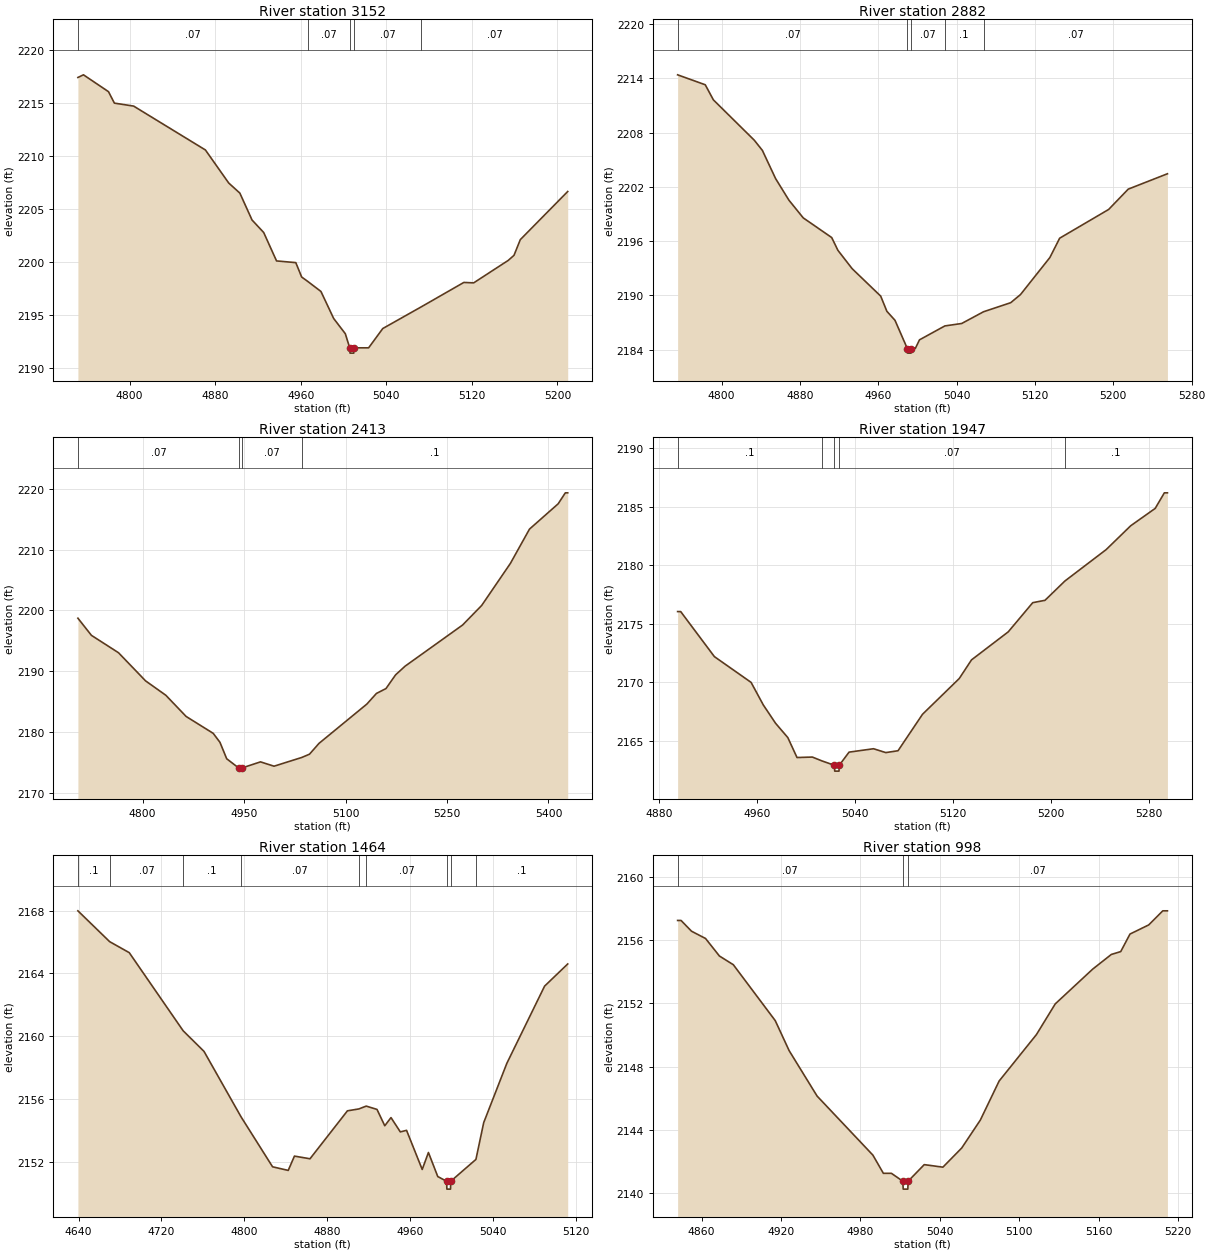
Type RM Length L Ch R = 1 ,3152    ,270,270,270
BEGIN DESCRIPTION:
Stream0263 7.0
END DESCRIPTION:
XS GIS Cut Line= 2
      1812024.35     13909902.24      1811604.33     13909719.87
#Sta/Elev= 30
  4751.7 2217.44  4756.9 2217.69  4780.3  2216.1  4785.8 2215.02  4803.8 2214.74
  4870.9  2210.6  4892.7 2207.48  4903.1 2206.53  4914.5 2203.99  4925.4 2202.81
  4937.4 2200.13  4955.4 2199.97  4960.9 2198.61  4966.4 2198.21  4978.9 2197.25
  4990.8  2194.7  5001.7 2193.26  5005.8 2191.93  5006.1 2191.43  5009.6 2191.43
  5009.8 2191.93  5023.5 2191.93  5036.7 2193.75  5072.4 2195.78  5112.5  2198.1
  5121.7 2198.06    5154 2200.18  5159.4 2200.66  5165.3 2202.14  5209.6 2206.68
#Mann= 5 ,-1 , 0
  4751.7     .07       0  4966.4     .07       0  5005.8     .05       0
  5009.8     .07       0  5072.4     .07       0
Bank Sta=5005.8,5009.8
XS Rating Curve= 0 ,0
Exp/Cntr=0.3,0.1

Type RM Length L Ch R = 1 ,2882    ,469,469,469
BEGIN DESCRIPTION:
Stream0263 6.0
END DESCRIPTION:
XS GIS Cut Line= 3
      1812075.02     13909775.03        1811925.       13909575.
      1811675.04       13909575.
#Sta/Elev= 30
  4755.2  2214.4  4783.4  2213.3  4791.7 2211.63  4833.4 2207.17  4841.7 2206.04
  4855.2 2202.92  4868.8 2200.53  4883.4 2198.57  4912.5 2196.39  4918.8 2194.98
  4933.4 2192.94  4962.5 2189.91  4968.8 2188.23  4977.1 2187.23  4989.7  2184.1
  4989.9  2183.6  4993.4  2183.6  4993.7  2184.1  4997.9 2184.13  5002.1 2185.07
    5028 2186.61  5045.2 2186.88  5067.5 2188.18  5095.2 2189.18  5105.2 2190.08
  5135.2 2194.18  5145.2 2196.32  5195.2  2199.5  5215.2 2201.75  5255.2 2203.45
#Mann= 5 ,-1 , 0
  4755.2     .07       0  4989.7     .05       0  4993.7     .07       0
    5028      .1       0  5067.5     .07       0
Bank Sta=4989.7,4993.7
XS Rating Curve= 0 ,0
Exp/Cntr=0.3,0.1

Type RM Length L Ch R = 1 ,2413    ,466,466,466
BEGIN DESCRIPTION:
Stream0263 5.0
END DESCRIPTION:
XS GIS Cut Line= 3
        1812275.     13909574.97        1812275.       13909275.
      1811975.02     13908975.02
#Sta/Elev= 30
  4704.3 2198.72  4724.3  2195.9  4764.3 2193.05  4804.3 2188.43  4834.3 2186.06
  4864.3 2182.58  4904.3 2179.81  4914.3 2178.34  4924.3 2175.63  4942.3  2174.1
  4942.5  2173.6    4946  2173.6  4946.3  2174.1  4974.3 2175.12  4994.3 2174.41
  5035.2 2175.84  5046.7 2176.38  5060.8 2178.16  5131.5 2184.61  5145.7 2186.36
  5159.8 2187.16    5174 2189.41  5188.1 2190.84    5273 2197.59  5301.3 2200.81
  5343.7 2207.71    5372 2213.35  5414.4 2217.51    5425 2219.31  5428.5 2219.31
#Mann= 4 ,-1 , 0
  4704.3     .07       0  4942.3     .05       0  4946.3     .07       0
  5035.2      .1       0
Bank Sta=4942.3,4946.3
XS Rating Curve= 0 ,0
Exp/Cntr=0.3,0.1

Type RM Length L Ch R = 1 ,1947    ,483,483,483
BEGIN DESCRIPTION:
Stream0263 4.0
END DESCRIPTION:
XS GIS Cut Line= 3
        1812725.     13909425.04        1812725.       13909325.
        1812725.     13909025.04
#Sta/Elev= 30
  4895.4 2176.04  4897.9 2176.04  4925.4  2172.2  4955.4    2170  4965.4 2168.07
  4975.4 2166.51  4985.4 2165.29  4992.9 2163.59  5005.4 2163.63  5013.3  2163.3
  5023.4 2162.93  5023.7 2162.43  5027.2 2162.43  5027.4 2162.93  5035.4 2164.05
  5055.4 2164.34  5065.4 2164.01  5075.4 2164.17  5095.4 2167.28  5125.4 2170.33
  5135.4 2171.92  5165.4 2174.31  5185.4  2176.8  5195.4    2177  5211.7 2178.65
  5245.4 2181.33  5265.4 2183.36  5285.4 2184.84  5292.9 2186.17  5295.4 2186.17
#Mann= 5 ,-1 , 0
  4895.4      .1       0  5013.3     .07       0  5023.4     .05       0
  5027.4     .07       0  5211.7      .1       0
Bank Sta=5023.4,5027.4
XS Rating Curve= 0 ,0
Exp/Cntr=0.3,0.1

Type RM Length L Ch R = 1 ,1464    ,466,466,466
BEGIN DESCRIPTION:
Stream0263 3.0
END DESCRIPTION:
XS GIS Cut Line= 3
      1813374.98     13909524.97        1813175.       13909225.
      1813125.01     13909125.02
#Sta/Elev= 30
  4639.4 2167.98    4670 2166.02  4688.9 2165.32  4740.9 2160.35    4761 2159.04
  4796.6 2154.89  4827.1  2151.7  4842.2 2151.47  4848.2 2152.38  4863.2 2152.21
  4899.3 2155.26  4910.3 2155.38  4917.4 2155.56  4927.8 2155.35  4935.3 2154.31
  4941.3 2154.83  4950.3 2153.92  4956.3 2154.02  4971.4 2151.53  4977.4 2152.61
  4986.4 2151.08  4994.9 2150.78  4995.2 2150.28  4998.7 2150.28  4998.9 2150.78
  5023.2 2152.17  5030.7 2154.51    5053 2158.28  5089.4 2163.19  5111.7  2164.6
#Mann= 9 ,-1 , 0
  4639.4      .1       0    4670     .07       0  4740.9      .1       0
  4796.6     .07       0  4910.3      .1       0  4917.4     .07       0
  4994.9     .05       0  4998.9     .07       0  5023.2      .1       0
Bank Sta=4994.9,4998.9
XS Rating Curve= 0 ,0
Exp/Cntr=0.3,0.1

Type RM Length L Ch R = 1 ,998     ,466,466,466
BEGIN DESCRIPTION:
Stream0263 2.0
END DESCRIPTION:
XS GIS Cut Line= 3
        1813575.     13909324.99        1813625.       13909175.
      1813475.02     13909025.02
#Sta/Elev= 30
  4841.9 2157.25  4844.5 2157.25  4852.4 2156.57    4863 2156.11  4873.5    2155
    4884 2154.45  4915.7 2150.91  4926.2 2149.01  4947.3 2146.14  4989.5  2142.4
  4997.4 2141.25  5003.5 2141.25  5012.1 2140.75  5012.4 2140.25  5015.9 2140.25
  5016.1 2140.75  5028.3  2141.8  5042.4 2141.64  5056.6 2142.85  5070.7 2144.62
  5084.9 2147.09  5113.1 2150.03  5127.3 2151.97  5155.6 2154.17  5169.7  2155.1
  5176.8 2155.28  5183.8 2156.39    5198 2156.97  5208.6 2157.86  5212.1 2157.86
#Mann= 3 ,-1 , 0
  4841.9     .07       0  5012.1     .05       0  5016.1     .07       0
Bank Sta=5012.1,5016.1
XS Rating Curve= 0 ,0
Exp/Cntr=0.3,0.1

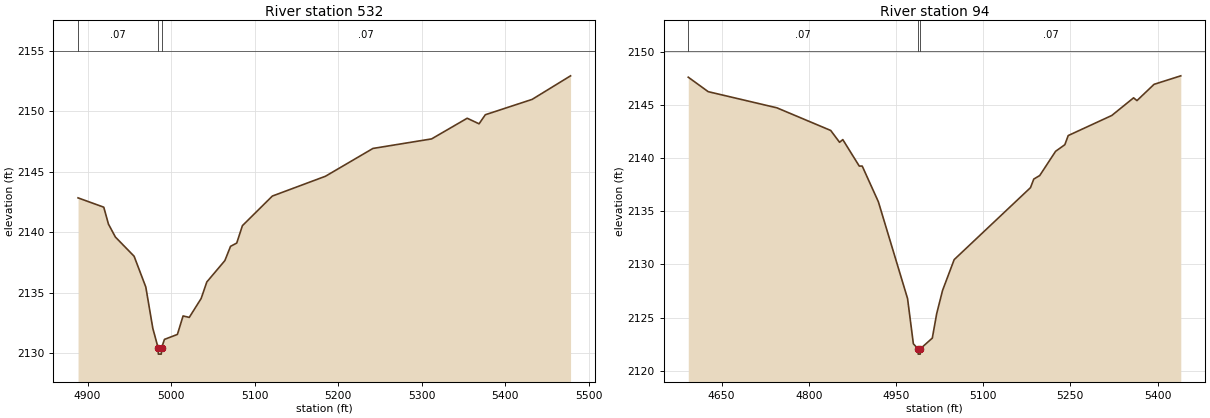
Type RM Length L Ch R = 1 ,532     ,438,438,438
BEGIN DESCRIPTION:
Stream0263 1.0
END DESCRIPTION:
XS GIS Cut Line= 3
      1814125.01     13909325.02        1814075.       13909225.
      1813720.28     13908905.24
#Sta/Elev= 30
  4888.6 2142.84  4919.4 2142.07    4925 2140.67  4933.3  2139.6  4955.7 2138.01
  4969.7 2135.46  4978.1 2132.04  4984.5 2130.41  4984.7 2129.91  4988.2 2129.91
  4988.5 2130.41    4992 2131.13  5007.5 2131.54  5014.3 2133.07  5021.7 2132.95
  5035.9 2134.51  5042.7 2135.88  5064.3 2137.65  5071.1 2138.83  5078.5  2139.1
  5085.3 2140.54  5121.1 2142.99  5184.7 2144.63  5241.5 2146.93  5311.7 2147.72
  5354.3 2149.43  5368.5 2148.97    5376 2149.72    5432 2150.99    5478 2152.94
#Mann= 3 ,-1 , 0
  4888.6     .07       0  4984.5     .05       0  4988.5     .07       0
Bank Sta=4984.5,4988.5
XS Rating Curve= 0 ,0
Exp/Cntr=0.3,0.1

Type RM Length L Ch R = 1 ,94      ,0,0,0
BEGIN DESCRIPTION:
Stream0263 0.0
END DESCRIPTION:
XS GIS Cut Line= 4
      1814410.29     13909521.14      1814489.81     13909235.48
      1814471.89      13909015.2      1814184.95     13908852.47
#Sta/Elev= 30
  4592.6 2147.61  4626.9 2146.25  4745.1 2144.73  4837.7  2142.6  4852.9 2141.49
  4858.5 2141.74  4886.8 2139.25  4891.9 2139.25  4919.7 2135.89  4969.9 2126.79
  4979.9 2122.53  4987.9 2122.06  4988.2 2121.56  4991.7 2121.56  4991.9 2122.06
  5012.5 2123.07    5020 2125.36  5030.1 2127.55  5050.1 2130.45  5181.4 2137.22
  5187.1 2138.03  5197.3 2138.36  5224.6 2140.64  5240.5 2141.26  5246.3 2142.12
  5321.3 2144.01  5358.8 2145.67  5364.6 2145.41    5394 2146.94    5440 2147.74
#Mann= 3 ,-1 , 0
  4592.6     .07       0  4987.9     .05       0  4991.9     .07       0
Bank Sta=4987.9,4991.9
XS Rating Curve= 0 ,0
Exp/Cntr=0.3,0.1

Chan Stop Cuts=-1
Use User Specified Reach Order=0
Composite Channel Slope=5