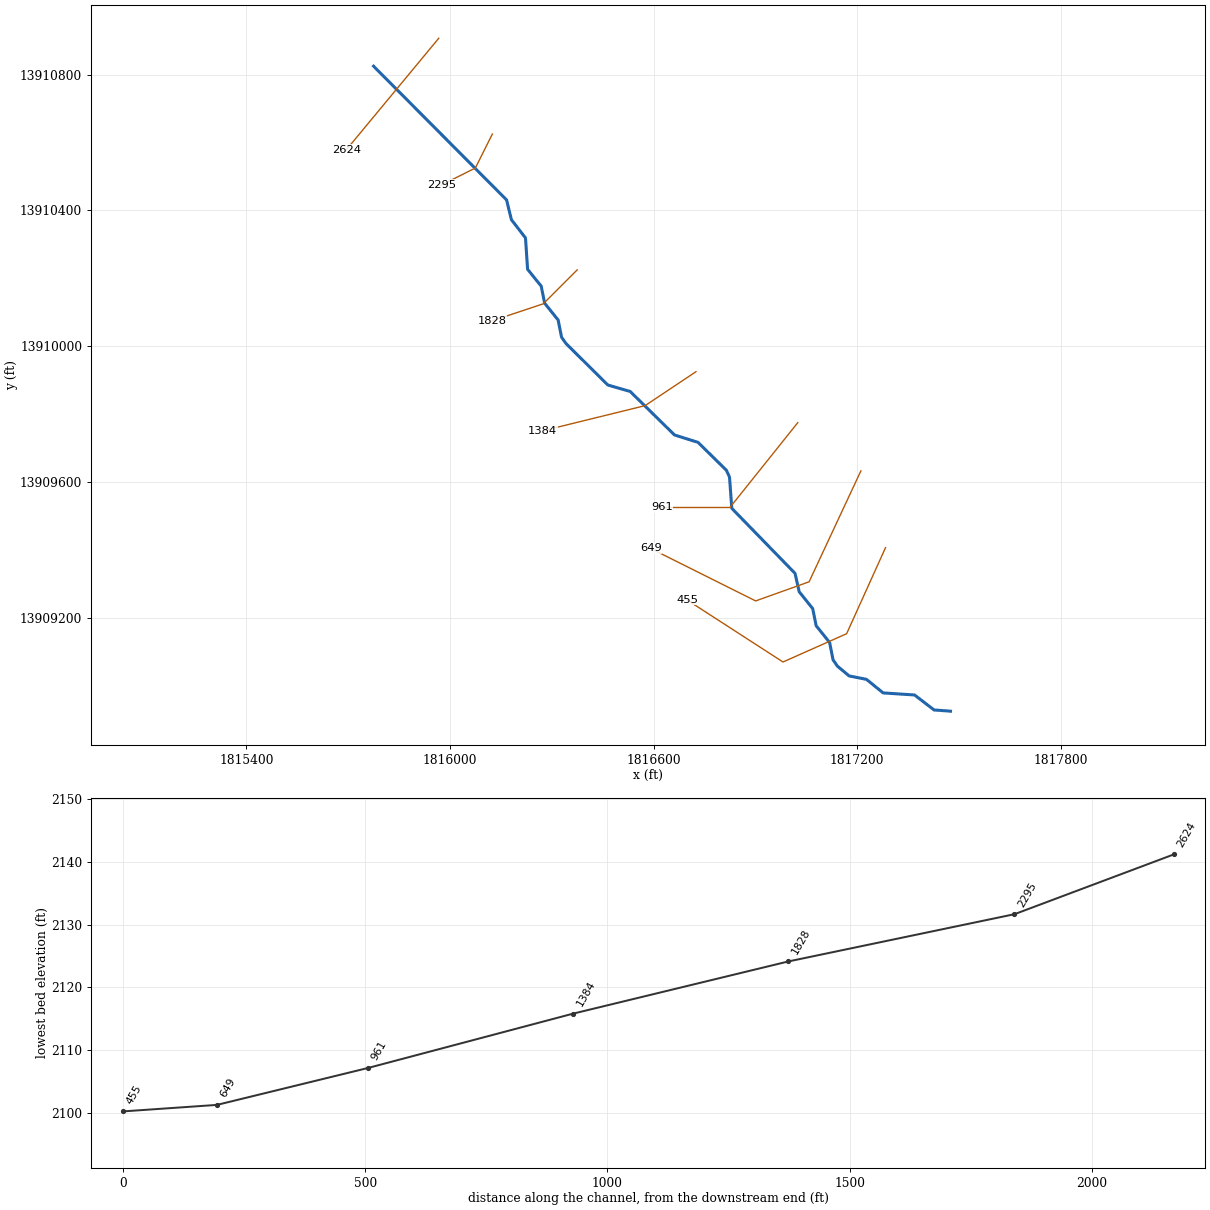
--- Stream0264.prj (project) ---

Proj Title=Stream0264 Base Level Engineering
Current Plan=p01
Default Exp/Contr=0.3,0.1
English Units
Geom File=g01
Flow File=f01
Plan File=p01
BEGIN DESCRIPTION:
Stream0264
END DESCRIPTION:

--- Stream0264.p01 (plan) ---

Plan Title=Multiple Run
Short Identifier=Multiple
Geom File=g01
Flow File=f01
Subcritical Flow
K Sum by GR= 0
Std Step Tol= 0.01
Critical Tol= 0.01
Num of Std Step Trials= 20
Max Error Tol= 0.3
Flow Tol Ratio= 0.001
Split Flow NTrial= 30
Split Flow Tol= 0.02
Split Flow Ratio= 0.02
Log Output Level= 0
Friction Slope Method= 1
Unsteady Friction Slope Method= 2
Unsteady Bridges Friction Slope Method= 1
Parabolic Critical Depth
Global Vel Dist=  1 , 1 , 1
Global Log Level= 0
CheckData=True
Encroach Param= -1, 0, 0, 0
BEGIN DESCRIPTION:
Multiple Run
END DESCRIPTION:

--- Stream0264.f01 (steady flow) ---

Flow Title=Multiple
Number of Profiles=7
Profile Names=10-year,25-year,50-year,1pct_min,100-year,1pct_plu,500-year
River Rch & RM= Stream0264,Reach-1,2624
     419     680     916     599    1195    2385    2008
Boundary for River Rch & Prof#=Stream0264,Reach-1,1
Up Type=0
Dn Type=3
Dn Slope=0.005
Boundary for River Rch & Prof#=Stream0264,Reach-1,2
Up Type=0
Dn Type=3
Dn Slope=0.005
Boundary for River Rch & Prof#=Stream0264,Reach-1,3
Up Type=0
Dn Type=3
Dn Slope=0.005
Boundary for River Rch & Prof#=Stream0264,Reach-1,4
Up Type=0
Dn Type=3
Dn Slope=0.005
Boundary for River Rch & Prof#=Stream0264,Reach-1,5
Up Type=0
Dn Type=3
Dn Slope=0.005
Boundary for River Rch & Prof#=Stream0264,Reach-1,6
Up Type=0
Dn Type=3
Dn Slope=0.005
Boundary for River Rch & Prof#=Stream0264,Reach-1,7
Up Type=0
Dn Type=3
Dn Slope=0.005

--- Stream0264.g01 (geometry) ---

Geom Title=Existing Conditions

River Reach=Stream0264,Reach-1
Reach XY= 30
      1815775.00     13910825.00      1816166.86     13910431.06
      1816181.14     13910372.83      1816222.67     13910319.03
      1816228.83     13910226.58      1816268.88     13910177.18
      1816279.16     13910126.72      1816318.90     13910077.19
      1816328.95     13910026.63      1816341.64     13910008.32
      1816465.32     13909885.78      1816531.05     13909866.84
      1816661.79     13909738.63      1816731.07     13909716.85
      1816814.49     13909634.81      1816823.84     13909614.52
      1816830.52     13909522.57      1817016.86     13909331.06
      1817029.19     13909276.74      1817068.92     13909227.20
      1817079.16     13909176.72      1817118.89     13909127.16
      1817128.86     13909076.42      1817141.49     13909057.94
      1817176.42     13909028.86      1817227.15     13909018.85
      1817276.58     13908978.82      1817369.08     13908972.77
      1817426.51     13908928.64      1817475.00     13908925.00

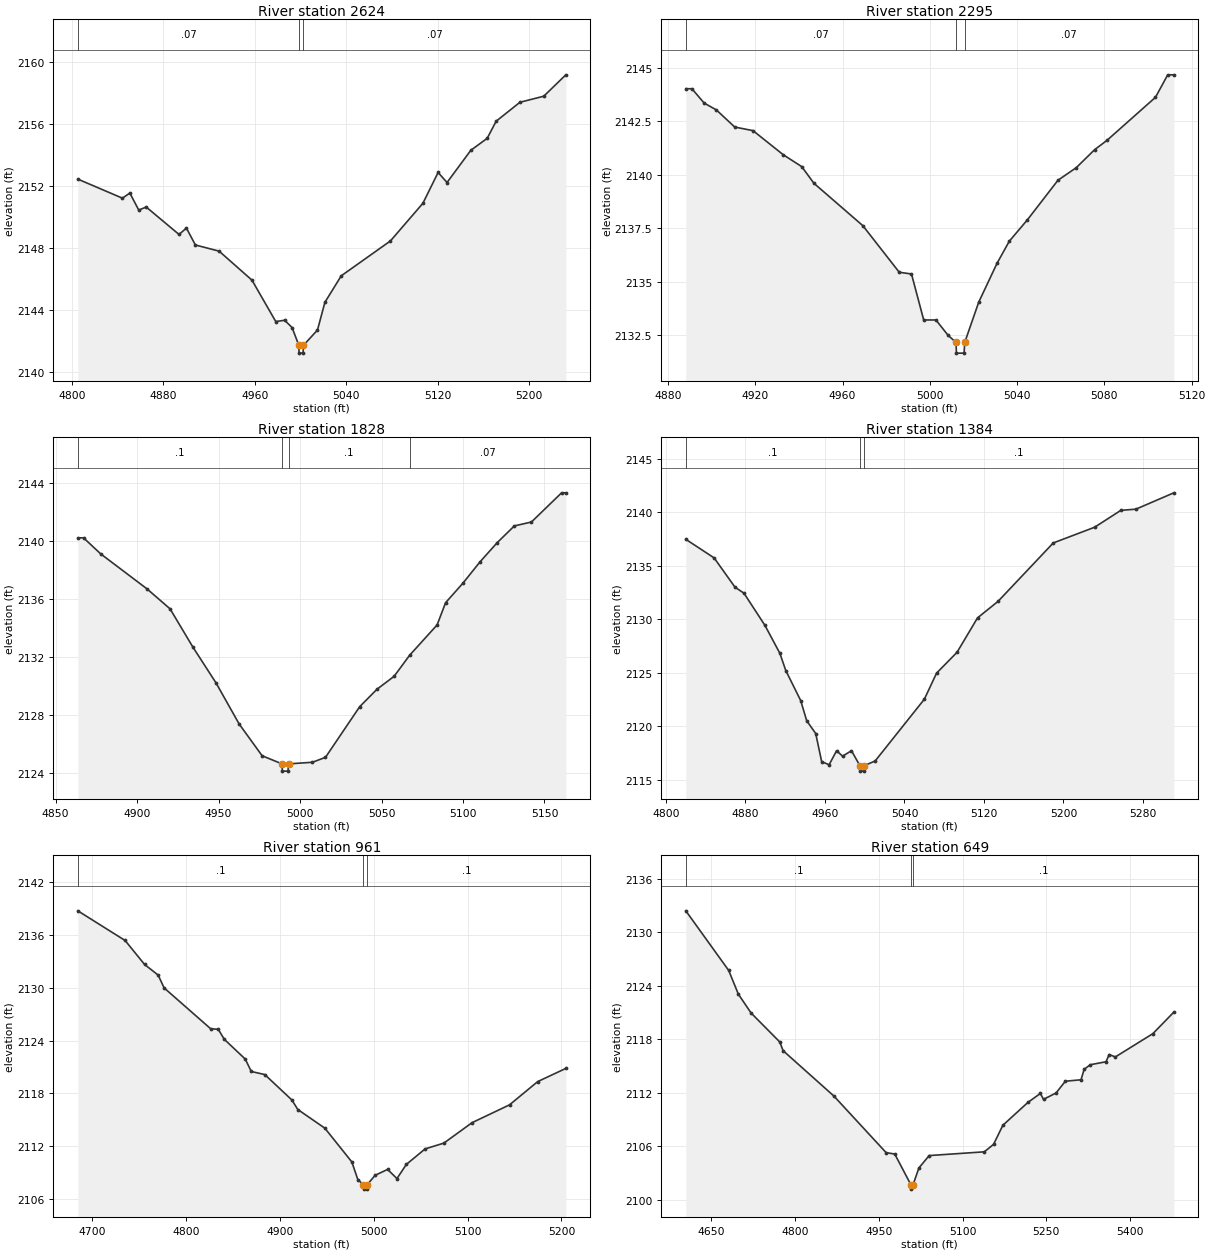
Type RM Length L Ch R = 1,2624,329,329,329
BEGIN DESCRIPTION:
Stream0264 5.0
END DESCRIPTION:
XS GIS Cut Line= 2
      1815967.11     13910907.33      1815694.73     13910578.75
#Sta/Elev= 30
  4805.1 2152.45  4844.1 2151.22  4850.6 2151.55  4858.4 2150.45  4864.9 2150.65
  4893.6 2148.88  4900.1 2149.29  4907.9 2148.20  4928.7 2147.80  4957.4 2145.93
  4978.2 2143.26  4986.0 2143.34  4992.5 2142.87  4998.4 2141.72  4998.6 2141.22
  5002.1 2141.22  5002.4 2141.72  5014.7 2142.71  5021.2 2144.50  5035.5 2146.21
  5078.5 2148.46  5106.9 2150.89  5120.2 2152.88  5128.0 2152.23  5148.8 2154.31
  5163.1 2155.08  5171.0 2156.19  5191.8 2157.41  5212.6 2157.80  5231.9 2159.18
#Mann=3,-1,0
  4805.1    0.07       0  4998.4    0.05       0  5002.4    0.07       0
Bank Sta=4998.4,5002.4
Exp/Cntr=0.3,0.1

Type RM Length L Ch R = 1,2295,467,467,467
BEGIN DESCRIPTION:
Stream0264 4.0
END DESCRIPTION:
XS GIS Cut Line= 3
      1816125.01     13910625.01      1816075.00     13910525.00
      1815975.02     13910475.01
#Sta/Elev= 30
  4888.2 2144.03  4891.0 2144.03  4896.6 2143.36  4902.2 2143.04  4910.6 2142.24
  4919.0 2142.07  4932.9 2140.94  4941.3 2140.39  4946.9 2139.61  4969.3 2137.63
  4986.0 2135.45  4991.6 2135.37  4997.2 2133.22  5002.8 2133.22  5008.4 2132.50
  5012.0 2132.17  5012.2 2131.67  5015.7 2131.67  5016.0 2132.17  5022.4 2134.05
  5030.8 2135.87  5036.4 2136.90  5044.7 2137.90  5058.7 2139.75  5067.1 2140.34
  5075.5 2141.18  5081.1 2141.61  5103.4 2143.63  5109.0 2144.68  5111.8 2144.68
#Mann=3,-1,0
  4888.2    0.07       0  5012.0    0.05       0  5016.0    0.07       0
Bank Sta=5012,5016
Exp/Cntr=0.3,0.1

Type RM Length L Ch R = 1,1828,444,444,444
BEGIN DESCRIPTION:
Stream0264 3.0
END DESCRIPTION:
XS GIS Cut Line= 3
      1816374.99     13910224.99      1816275.00     13910125.00
      1816125.02     13910075.01
#Sta/Elev= 28
  4863.6 2140.19  4867.1 2140.19  4877.7 2139.08  4906.0 2136.68  4920.2 2135.30
  4934.3 2132.65  4948.4 2130.20  4962.6 2127.37  4976.7 2125.18  4988.9 2124.62
  4989.1 2124.12  4992.6 2124.12  4992.9 2124.62  5007.6 2124.73  5015.6 2125.07
  5036.6 2128.56  5047.2 2129.76  5057.7 2130.65  5067.3 2132.11  5084.1 2134.19
  5089.3 2135.72  5099.9 2137.06  5110.4 2138.53  5121.0 2139.86  5131.5 2141.01
  5142.0 2141.28  5160.5 2143.29  5163.1 2143.29
#Mann=4,-1,0
  4863.6     0.1       0  4988.9    0.05       0  4992.9     0.1       0
  5067.3    0.07       0
Bank Sta=4988.9,4992.9
Exp/Cntr=0.3,0.1

Type RM Length L Ch R = 1,1384,423,423,423
BEGIN DESCRIPTION:
Stream0264 2.0
END DESCRIPTION:
XS GIS Cut Line= 3
      1816724.96     13909924.98      1816575.00     13909825.00
      1816273.22     13909750.82
#Sta/Elev= 30
  4820.0 2137.48  4848.5 2135.74  4869.5 2133.00  4878.5 2132.44  4899.6 2129.43
  4914.6 2126.82  4920.6 2125.20  4935.6 2122.39  4941.6 2120.51  4950.7 2119.31
  4956.7 2116.67  4964.2 2116.39  4971.7 2117.70  4977.7 2117.19  4986.7 2117.70
  4995.2 2116.29  4995.5 2115.79  4999.0 2115.79  4999.2 2116.29  5010.5 2116.74
  5060.0 2122.52  5072.3 2124.96  5092.9 2126.91  5113.5 2130.13  5134.1 2131.67
  5189.7 2137.14  5231.3 2138.61  5257.7 2140.19  5272.8 2140.30  5311.0 2141.83
#Mann=3,-1,0
  4820.0     0.1       0  4995.2    0.05       0  4999.2     0.1       0
Bank Sta=4995.2,4999.2
Exp/Cntr=0.3,0.1

Type RM Length L Ch R = 1,961,312,312,312
BEGIN DESCRIPTION:
Stream0264 1.0
END DESCRIPTION:
XS GIS Cut Line= 3
      1817025.00     13909775.00      1816825.00     13909525.00
      1816624.95     13909525.00
#Sta/Elev= 30
  4684.5 2138.75  4734.9 2135.38  4755.7 2132.65  4770.1 2131.45  4776.5 2129.99
  4826.2 2125.34  4834.2 2125.29  4840.6 2124.15  4863.0 2121.90  4869.4 2120.49
  4883.8 2120.14  4912.6 2117.26  4919.0 2116.17  4947.8 2114.05  4976.6 2110.21
  4983.0 2108.20  4989.0 2107.62  4989.3 2107.12  4992.8 2107.12  4993.0 2107.62
  5001.4 2108.69  5014.7 2109.36  5024.7 2108.32  5034.7 2109.93  5054.7 2111.69
  5074.7 2112.35  5104.7 2114.67  5144.7 2116.70  5174.7 2119.34  5204.7 2120.84
#Mann=3,-1,0
  4684.5     0.1       0  4989.0    0.05       0  4993.0     0.1       0
Bank Sta=4989,4993
Exp/Cntr=0.3,0.1

Type RM Length L Ch R = 1,649,194,194,194
BEGIN DESCRIPTION:
Stream0264 0.0
END DESCRIPTION:
XS GIS Cut Line= 4
      1817210.94     13909632.84      1817058.35     13909306.12
      1816900.87     13909249.82      1816591.41     13909404.27
#Sta/Elev= 30
  4604.6 2132.40  4681.4 2125.72  4698.7 2123.06  4721.5 2120.95  4772.8 2117.71
  4778.8 2116.73  4869.7 2111.65  4963.2 2105.31  4978.7 2105.15  5007.5 2101.72
  5007.8 2101.22  5011.5 2101.72  5021.9 2103.59  5040.3 2104.98  5139.0 2105.40
  5155.5 2106.23  5172.3 2108.38  5217.0 2110.93  5239.4 2111.94  5245.0 2111.28
  5267.4 2111.99  5284.1 2113.31  5312.1 2113.47  5317.8 2114.65  5328.9 2115.16
  5356.9 2115.49  5362.5 2116.30  5373.6 2116.03  5440.8 2118.64  5478.3 2121.05
#Mann=3,-1,0
  4604.6     0.1       0  5007.5    0.05       0  5011.5     0.1       0
Bank Sta=5007.5,5011.5
Exp/Cntr=0.3,0.1

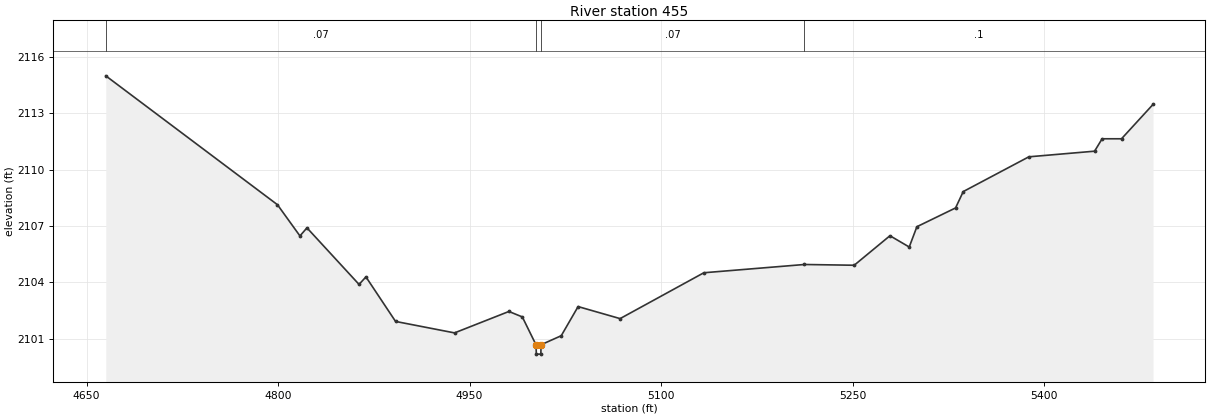
Type RM Length L Ch R = 1,455,0,0,0
BEGIN DESCRIPTION:
Stream0262 0.1
END DESCRIPTION:
XS GIS Cut Line= 4
      1817283.53     13909406.71      1817168.94     13909153.23
      1816981.44     13909069.90      1816698.39     13909252.85
#Sta/Elev= 30
  4665.0 2114.99  4799.5 2108.13  4817.1 2106.47  4822.6 2106.90  4863.4 2103.89
  4868.8 2104.29  4892.0 2101.92  4938.2 2101.31  4980.8 2102.45  4991.3 2102.16
  5002.0 2100.68  5002.3 2100.18  5005.8 2100.18  5006.0 2100.68  5021.8 2101.16
  5035.0 2102.71  5067.9 2102.07  5133.5 2104.51  5212.3 2104.95  5251.3 2104.91
  5279.3 2106.48  5294.4 2105.88  5300.4 2106.96  5330.7 2107.96  5336.7 2108.83
  5388.1 2110.68  5439.6 2110.98  5445.5 2111.64  5460.7 2111.64  5485.4 2113.47
#Mann=4,-1,0
  4665.0    0.07       0  5002.0    0.05       0  5006.0    0.07       0
  5212.3     0.1       0
Bank Sta=5002,5006
Exp/Cntr=0.3,0.1

Chan Stop Cuts=-1