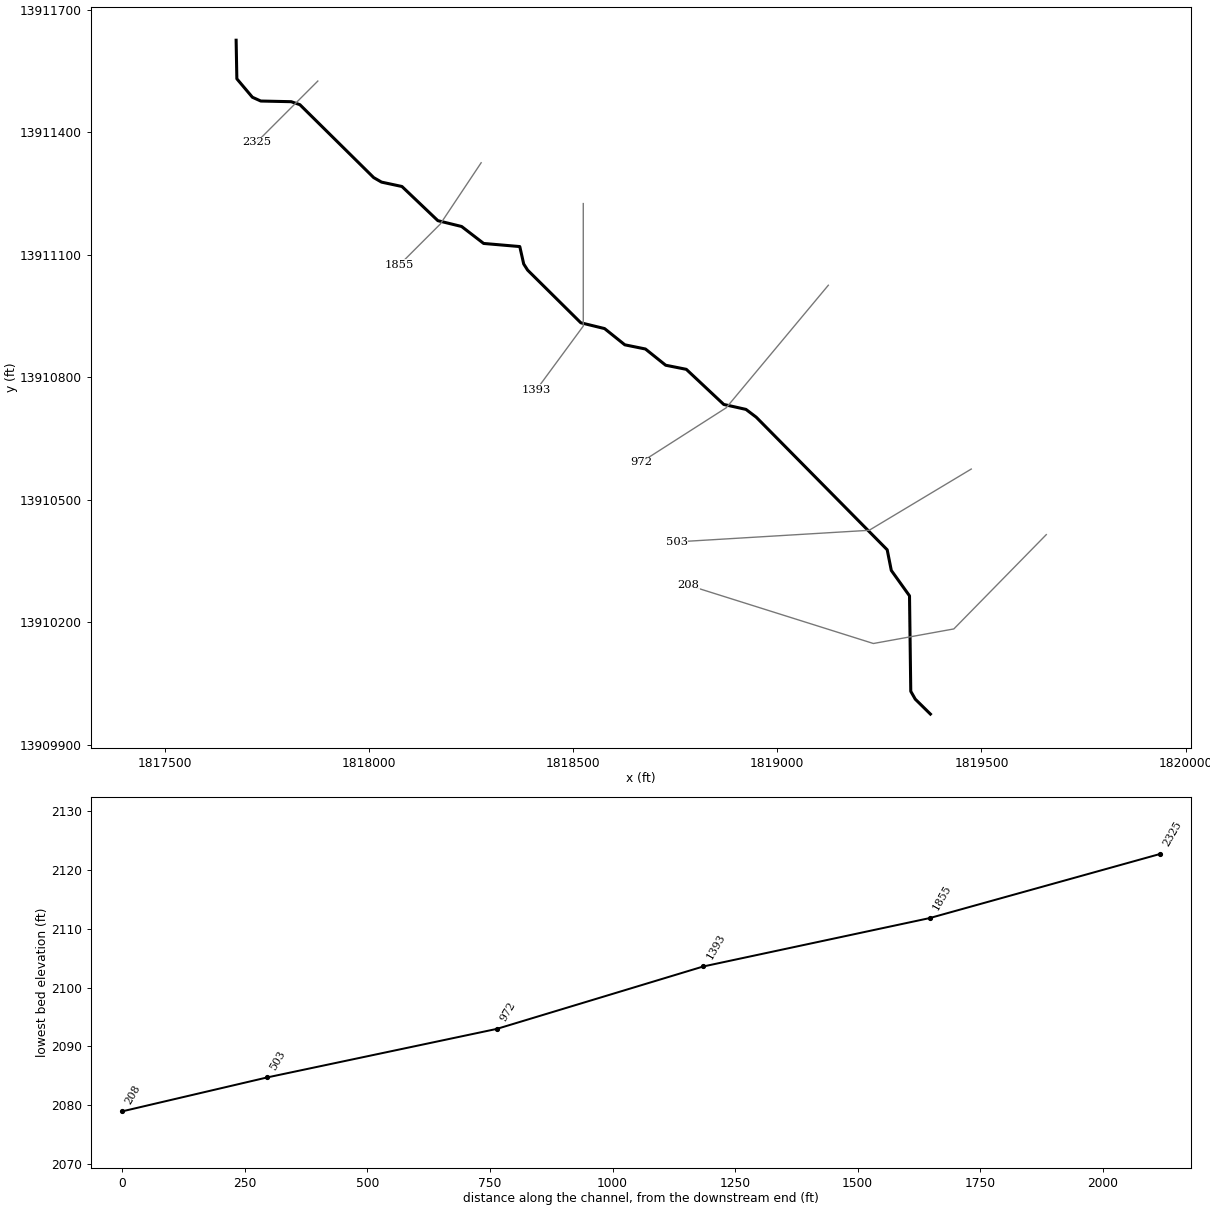
--- Stream0265.prj (project) ---

Proj Title=Stream0265 Base Level Engineering
Current Plan=p01
Default Exp/Contr=0.3,0.1
English Units
Geom File=g01
Flow File=f01
Plan File=p01
Y Axis Title=Elevation
X Axis Title(PF)=Main Channel Distance
X Axis Title(XS)=Station
BEGIN DESCRIPTION:
Stream0265
END DESCRIPTION:
DSS Export Rating Curves= 0
DSS Export Rating Curve Sorted= 0
DSS Export Volume Flow Curves= 0
DXF OffsetX= 0
DXF OffsetY= 0
DXF ScaleX= 1
DXF ScaleY= 10

--- Stream0265.p01 (plan) ---

Plan Title=Multiple Run
Short Identifier=Multiple
Geom File=g01
Flow File=f01
Subcritical Flow
K Sum by GR= 0
Std Step Tol= 0.01
Critical Tol= 0.01
Num of Std Step Trials= 20
Max Error Tol= 0.3
Flow Tol Ratio= 0.001
Split Flow NTrial= 30
Split Flow Tol= 0.02
Split Flow Ratio= 0.02
Log Output Level= 0
Friction Slope Method= 1
Unsteady Friction Slope Method= 2
Unsteady Bridges Friction Slope Method= 1
Parabolic Critical Depth
Global Vel Dist=  1 , 1 , 1
Global Log Level= 0
CheckData=True
Encroach Param= -1, 0, 0, 0
BEGIN DESCRIPTION:
Multiple Run
END DESCRIPTION:

--- Stream0265.f01 (steady flow) ---

Flow Title=Multiple
Number of Profiles=7
Profile Names=10-year,25-year,50-year,1pct_min,100-year,1pct_plu,500-year
River Rch & RM= Stream0265,Reach-1,2325
     455     742    1003     658    1314    2621    2222
Boundary for River Rch & Prof#=Stream0265,Reach-1,1
Up Type=0
Dn Type=3
Dn Slope=0.005
Boundary for River Rch & Prof#=Stream0265,Reach-1,2
Up Type=0
Dn Type=3
Dn Slope=0.005
Boundary for River Rch & Prof#=Stream0265,Reach-1,3
Up Type=0
Dn Type=3
Dn Slope=0.005
Boundary for River Rch & Prof#=Stream0265,Reach-1,4
Up Type=0
Dn Type=3
Dn Slope=0.005
Boundary for River Rch & Prof#=Stream0265,Reach-1,5
Up Type=0
Dn Type=3
Dn Slope=0.005
Boundary for River Rch & Prof#=Stream0265,Reach-1,6
Up Type=0
Dn Type=3
Dn Slope=0.005
Boundary for River Rch & Prof#=Stream0265,Reach-1,7
Up Type=0
Dn Type=3
Dn Slope=0.005

--- Stream0265.g01 (geometry) ---

Geom Title=Existing Conditions
Program Version=4.10

River Reach=Stream0265      ,Reach-1
Reach XY= 30
        1817675.       13911625.      1817676.76     13911530.53
      1817714.84     13911485.34      1817735.32     13911476.09
      1817809.78     13911474.47      1817831.17     13911467.14
      1818011.79     13911288.63      1818031.05     13911277.53
      1818081.04     13911266.82      1818168.95     13911183.16
      1818227.17     13911168.86      1818281.05     13911127.37
      1818369.53     13911119.74      1818379.15     13911077.08
      1818388.74     13911062.05      1818518.94     13910933.14
      1818577.19      13910918.9      1818626.72     13910879.16
       1818677.2     13910868.92      1818726.74     13910829.19
      1818777.29     13910819.15      1818868.96     13910733.18
      1818923.35     13910721.03      1818948.47     13910701.99
      1819269.17      13910377.3      1819279.22     13910326.75
       1819323.8      13910264.5      1819326.89     13910030.78
      1819337.92     13910011.49        1819375.       13909975.

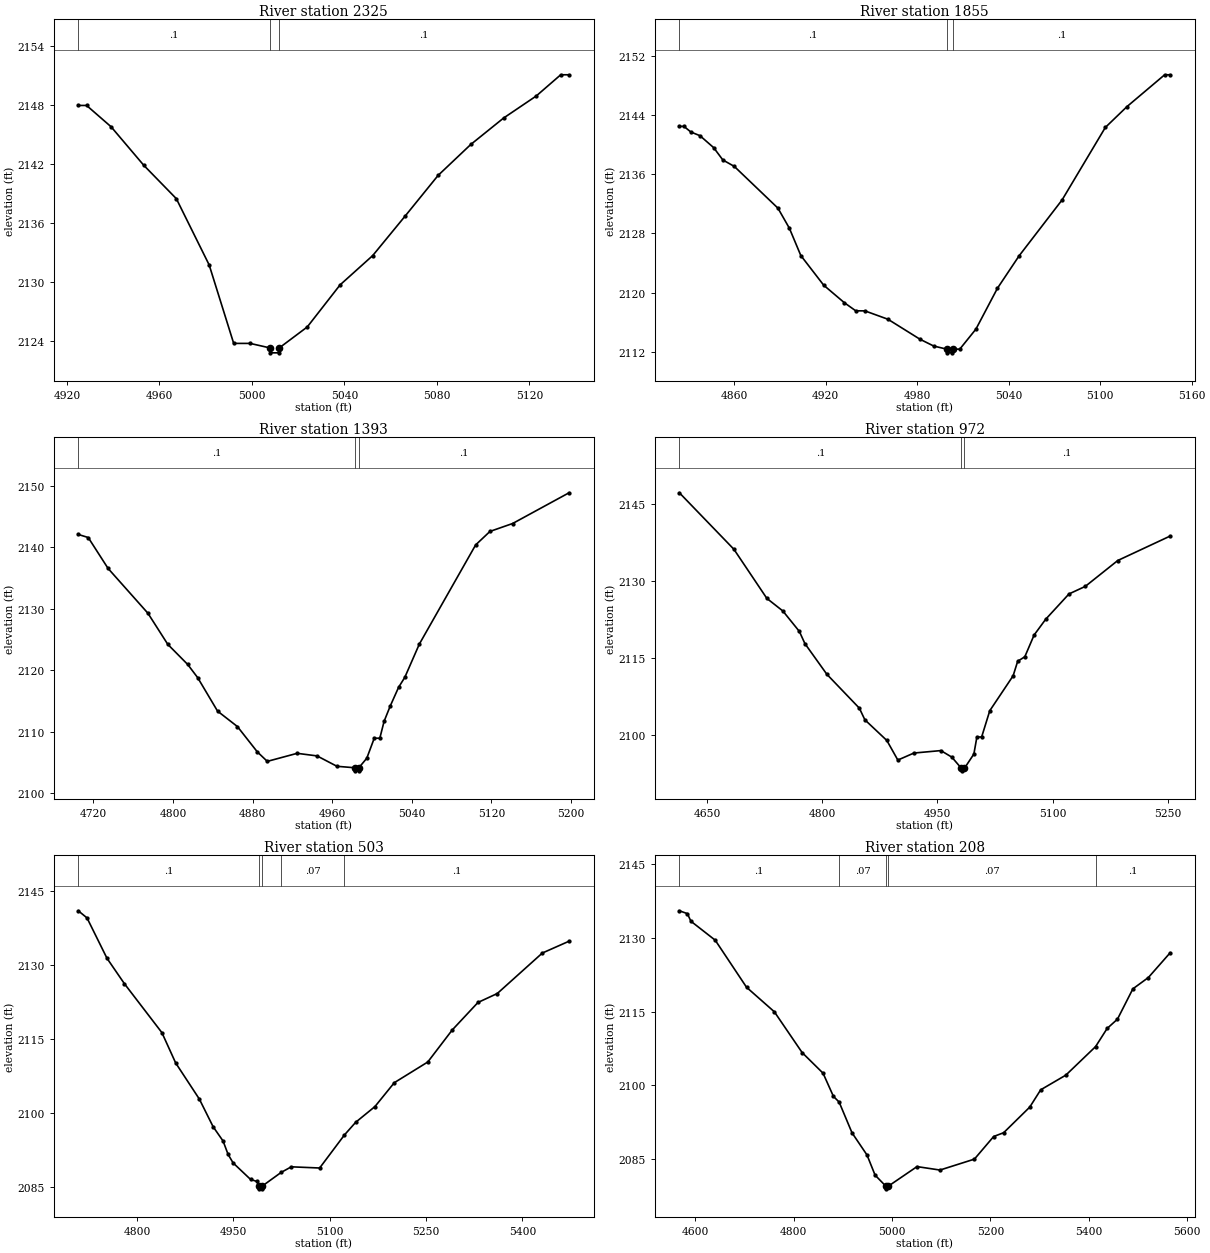
Type RM Length L Ch R = 1 ,2325    ,470,470,470
BEGIN DESCRIPTION:
Stream0265 5.0
END DESCRIPTION:
XS GIS Cut Line= 3
      1817875.02     13911525.02        1817825.       13911475.
      1817724.97     13911374.97
#Sta/Elev= 22
  4924.9 2147.92  4928.5 2147.92  4939.1 2145.75  4953.2 2141.84  4967.3 2138.44
  4981.5  2131.7  4992.1 2123.72  4999.2 2123.72  5007.8 2123.26    5008 2122.76
  5011.5 2122.76  5011.8 2123.26  5023.9 2125.39  5038.1 2129.67  5052.2 2132.65
  5066.3 2136.69  5080.5 2140.81  5094.6 2143.95  5108.8 2146.64  5122.9 2148.88
  5133.5 2151.04  5137.1 2151.04
#Mann= 3 ,-1 , 0
  4924.9      .1       0  5007.8     .05       0  5011.8      .1       0
Bank Sta=5007.8,5011.8
XS Rating Curve= 0 ,0
Exp/Cntr=0.3,0.1

Type RM Length L Ch R = 1 ,1855    ,462,462,462
BEGIN DESCRIPTION:
Stream0265 4.0
END DESCRIPTION:
XS GIS Cut Line= 3
      1818274.97     13911324.96        1818175.       13911175.
      1818074.97     13911074.97
#Sta/Elev= 30
  4824.2 2142.45  4827.2 2142.45  4831.7 2141.69  4837.7 2141.19  4846.7 2139.57
  4852.7 2137.91  4860.2 2137.04  4888.8  2131.4  4896.3 2128.69  4903.8    2125
  4918.8 2120.99  4932.3 2118.63  4939.8 2117.53  4945.8 2117.52  4960.9 2116.39
  4981.9 2113.69  4990.9 2112.77  4999.4 2112.35  4999.7 2111.85  5003.2 2111.85
  5003.4 2112.35    5008 2112.35  5018.6 2115.06  5032.7 2120.58  5046.9 2124.96
  5075.1 2132.52  5103.4  2142.3  5117.6 2145.12  5142.3 2149.42  5145.9 2149.42
#Mann= 3 ,-1 , 0
  4824.2      .1       0  4999.4     .05       0  5003.4      .1       0
Bank Sta=4999.4,5003.4
XS Rating Curve= 0 ,0
Exp/Cntr=0.3,0.1

Type RM Length L Ch R = 1 ,1393    ,421,421,421
BEGIN DESCRIPTION:
Stream0265 3.0
END DESCRIPTION:
XS GIS Cut Line= 3
        1818525.     13911225.03        1818525.       13910925.
      1818410.45     13910769.34
#Sta/Elev= 30
  4704.7 2142.08  4714.7 2141.58  4734.7 2136.54  4774.7 2129.26  4794.7 2124.19
  4814.7 2120.92  4824.7 2118.78  4844.7 2113.33  4864.7 2110.81  4884.7 2106.69
  4894.7 2105.15  4924.7 2106.46  4944.7 2106.04  4964.7 2104.35  4982.7 2104.11
    4983 2103.61  4986.5 2103.61  4986.7 2104.11  4994.7 2105.66  5002.2 2108.92
  5007.8 2108.92  5012.1 2111.67  5018.3 2114.17  5026.7 2117.21  5032.9 2118.82
  5047.5 2124.23  5104.1 2140.37  5118.5 2142.57  5141.3 2143.86    5198 2148.86
#Mann= 3 ,-1 , 0
  4704.7      .1       0  4982.7     .05       0  4986.7      .1       0
Bank Sta=4982.7,4986.7
XS Rating Curve= 0 ,0
Exp/Cntr=0.3,0.1

Type RM Length L Ch R = 1 ,972     ,469,469,469
BEGIN DESCRIPTION:
Stream0265 2.0
END DESCRIPTION:
XS GIS Cut Line= 3
      1819125.01     13911025.01        1818875.       13910725.
      1818665.77     13910591.17
#Sta/Elev= 30
  4614.1 2147.22  4685.1  2136.2    4728 2126.62  4748.8 2124.17  4770.3 2120.18
  4777.5 2117.81  4806.1 2111.82  4848.4 2105.21  4855.6 2102.94  4884.2 2098.91
  4898.5 2095.09  4919.4 2096.46  4954.5 2096.94  4968.8 2095.66  4981.2 2093.49
  4981.4 2092.99  4985.2 2093.49  4997.5 2096.27  5001.4 2099.59  5007.6 2099.59
  5018.2 2104.72  5048.6 2111.53  5054.5 2114.36  5063.8 2115.24  5075.9 2119.48
  5090.9 2122.54  5121.3 2127.49  5142.5 2128.96  5184.8 2134.01    5253 2138.78
#Mann= 3 ,-1 , 0
  4614.1      .1       0  4981.2     .05       0  4985.2      .1       0
Bank Sta=4981.2,4985.2
XS Rating Curve= 0 ,0
Exp/Cntr=0.3,0.1

Type RM Length L Ch R = 1 ,503     ,295,295,295
BEGIN DESCRIPTION:
Stream0265 1.0
END DESCRIPTION:
XS GIS Cut Line= 3
      1819474.98     13910574.99        1819225.       13910425.
      1818753.47      13910396.6
#Sta/Elev= 30
  4708.7 2140.91  4722.3 2139.47  4753.4 2131.31  4780.6 2126.16  4838.9 2116.28
  4860.3 2110.16  4897.2 2102.85  4918.6 2097.27  4934.1 2094.38  4941.9 2091.68
  4949.7 2089.96  4976.9 2086.62  4986.6 2086.22  4990.4 2085.22  4990.7 2084.72
  4994.2 2084.72  4994.4 2085.22  5024.5 2088.04  5040.3 2089.17  5084.4 2088.93
    5123 2095.61  5140.5 2098.17  5170.5 2101.35  5200.6 2106.17  5252.7 2110.35
  5290.7 2116.81  5330.8 2122.38  5360.9 2124.19    5431 2132.37  5472.6 2134.76
#Mann= 5 ,-1 , 0
  4708.7      .1       0  4990.4     .05       0  4994.4      .1       0
  5024.5     .07       0    5123      .1       0
Bank Sta=4990.4,4994.4
XS Rating Curve= 0 ,0
Exp/Cntr=0.3,0.1

Type RM Length L Ch R = 1 ,208     ,0,0,0
BEGIN DESCRIPTION:
Stream0265 0.0
END DESCRIPTION:
XS GIS Cut Line= 4
      1819658.71     13910414.39      1819432.38     13910183.51
      1819235.35      13910147.8       1818782.7     13910290.31
#Sta/Elev= 30
  4567.6 2135.49  4583.9 2134.91    4591 2133.37  4640.5 2129.51  4704.2 2119.94
  4760.8 2114.95  4817.3 2106.66  4859.8 2102.47  4880.9 2097.76  4892.5  2096.6
  4918.7 2090.35  4949.2 2085.84  4965.6 2081.75  4987.9 2079.46  4988.1 2078.96
  4991.9 2079.46  5050.9 2083.48  5097.6 2082.78  5167.6    2085  5206.8  2089.6
  5227.1 2090.37  5280.2 2095.58  5302.4 2099.09  5353.6 2102.08    5414 2107.87
  5437.5 2111.56  5458.5 2113.45  5489.9 2119.62  5521.4 2121.92  5565.7 2126.95
#Mann= 5 ,-1 , 0
  4567.6      .1       0  4892.5     .07       0  4987.9     .05       0
  4991.9     .07       0    5414      .1       0
Bank Sta=4987.9,4991.9
XS Rating Curve= 0 ,0
Exp/Cntr=0.3,0.1

Chan Stop Cuts=-1
Use User Specified Reach Order=0
Composite Channel Slope=5