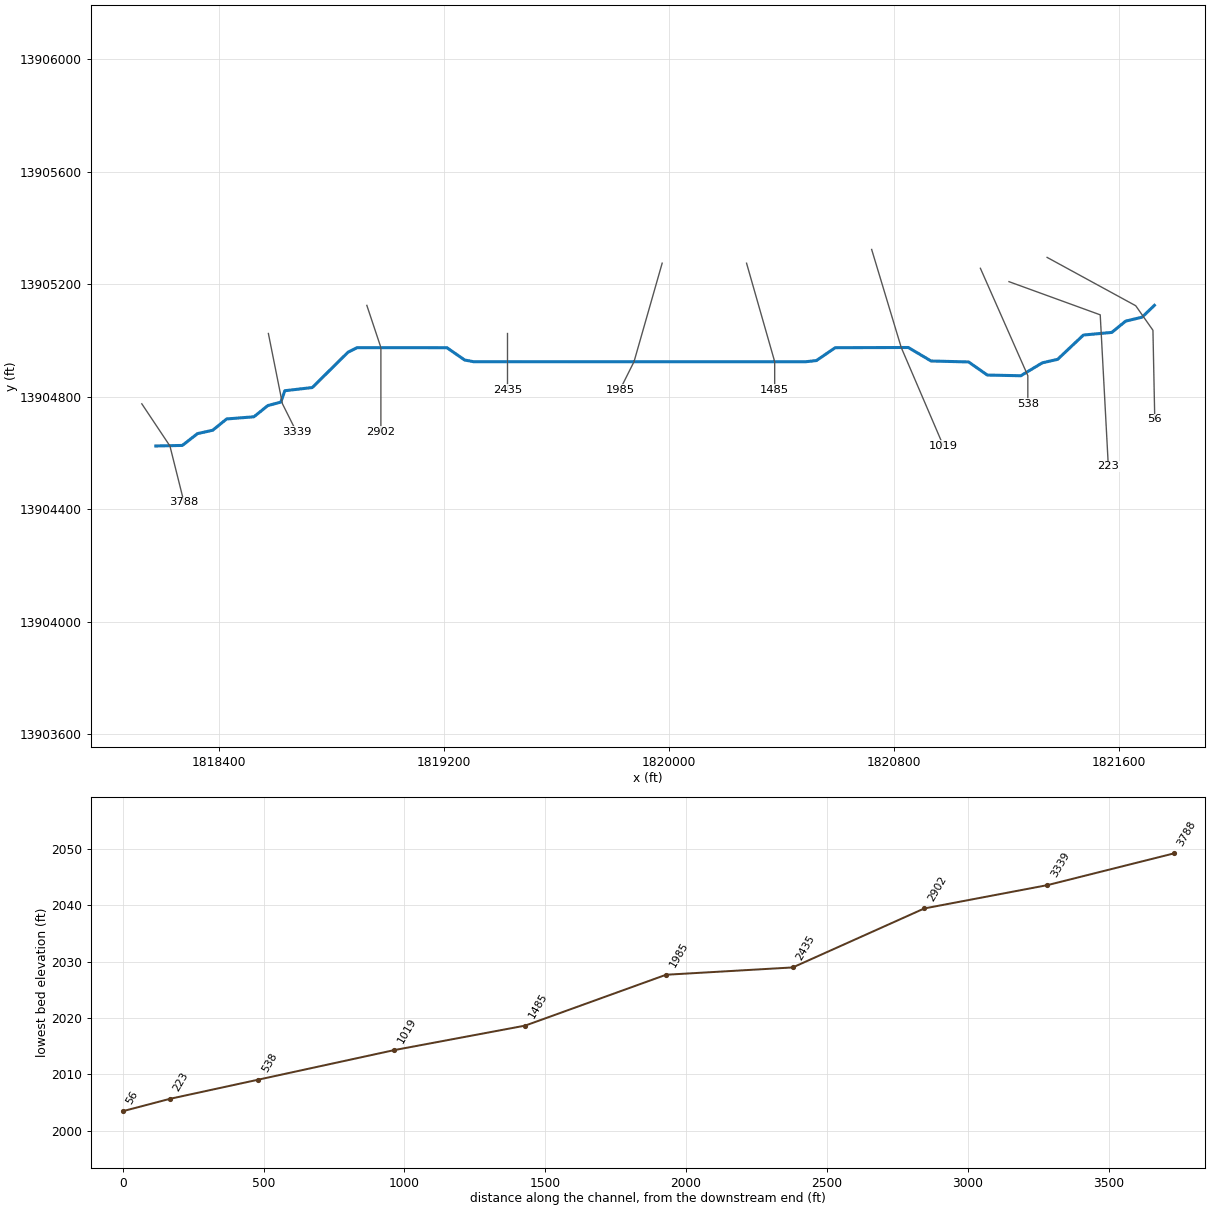
--- Stream0269.prj (project) ---

Proj Title=Stream0269 Base Level Engineering
Current Plan=p01
Default Exp/Contr=0.3,0.1
English Units
Geom File=g01
Flow File=f01
Plan File=p01
BEGIN DESCRIPTION:
Stream0269
END DESCRIPTION:

--- Stream0269.p01 (plan) ---

Plan Title=Multiple Run
Short Identifier=Multiple
Geom File=g01
Flow File=f01
Subcritical Flow
K Sum by GR= 0
Std Step Tol= 0.01
Critical Tol= 0.01
Num of Std Step Trials= 20
Max Error Tol= 0.3
Flow Tol Ratio= 0.001
Split Flow NTrial= 30
Split Flow Tol= 0.02
Split Flow Ratio= 0.02
Log Output Level= 0
Friction Slope Method= 1
Unsteady Friction Slope Method= 2
Unsteady Bridges Friction Slope Method= 1
Parabolic Critical Depth
Global Vel Dist=  1 , 1 , 1
Global Log Level= 0
CheckData=True
Encroach Param= -1, 0, 0, 0
BEGIN DESCRIPTION:
Multiple Run
END DESCRIPTION:

--- Stream0269.f01 (steady flow) ---

Flow Title=Multiple
Number of Profiles=7
Profile Names=10-year,25-year,50-year,1pct_min,100-year,1pct_plu,500-year
River Rch & RM= Stream0269,Reach-1,3788
    1758    3123    4470    3089    6163   12297   11597
Boundary for River Rch & Prof#=Stream0269,Reach-1,1
Up Type=0
Dn Type=3
Dn Slope=0.005
Boundary for River Rch & Prof#=Stream0269,Reach-1,2
Up Type=0
Dn Type=3
Dn Slope=0.005
Boundary for River Rch & Prof#=Stream0269,Reach-1,3
Up Type=0
Dn Type=3
Dn Slope=0.005
Boundary for River Rch & Prof#=Stream0269,Reach-1,4
Up Type=0
Dn Type=3
Dn Slope=0.005
Boundary for River Rch & Prof#=Stream0269,Reach-1,5
Up Type=0
Dn Type=3
Dn Slope=0.005
Boundary for River Rch & Prof#=Stream0269,Reach-1,6
Up Type=0
Dn Type=3
Dn Slope=0.005
Boundary for River Rch & Prof#=Stream0269,Reach-1,7
Up Type=0
Dn Type=3
Dn Slope=0.005

--- Stream0269.g01 (geometry) ---

Geom Title=Existing Conditions

River Reach=Stream0269,Reach-1
Reach XY= 30
      1818175.00     13904625.00      1818269.14     13904627.07
      1818322.81     13904668.91      1818377.18     13904681.11
      1818426.59     13904721.17      1818523.44     13904728.82
      1818573.13     13904768.79      1818619.21     13904781.02
      1818633.48     13904821.50      1818731.13     13904832.88
      1818858.24     13904958.57      1818890.16     13904974.62
      1819209.78     13904974.48      1819272.67     13904930.75
      1819304.85     13904924.64      1820485.19     13904924.55
      1820523.43     13904928.78      1820590.22     13904974.48
      1820850.08     13904975.20      1820930.94     13904927.27
      1821064.49     13904923.77      1821130.94     13904877.25
      1821250.08     13904874.76      1821326.75     13904920.78
      1821381.05     13904933.16      1821472.58     13905019.46
      1821573.42     13905028.82      1821622.78     13905068.97
      1821681.15     13905082.91      1821725.00     13905125.00

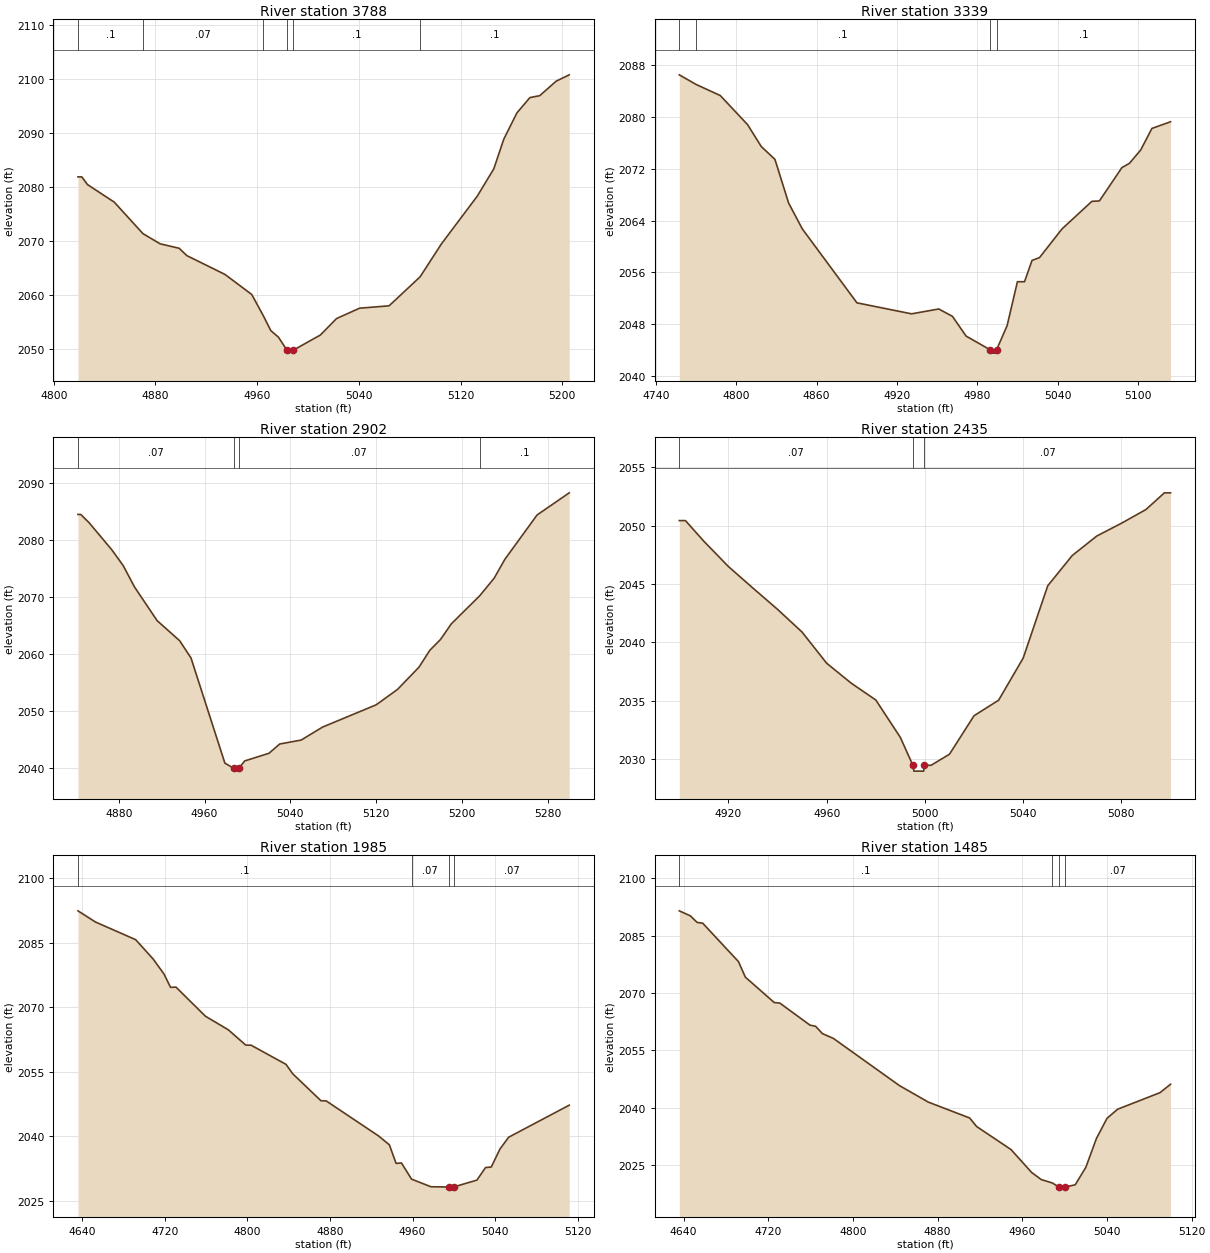
Type RM Length L Ch R = 1,3788,449,449,449
BEGIN DESCRIPTION:
Stream0269 8.0
END DESCRIPTION:
XS GIS Cut Line= 3
      1818125.02     13904774.98      1818225.00     13904625.00
      1818275.00     13904425.00
#Sta/Elev= 30
  4819.1 2081.87  4822.1 2081.87  4826.6 2080.44  4847.6 2077.19  4870.2 2071.34
  4883.7 2069.45  4898.7 2068.62  4904.7 2067.26  4934.7 2063.77  4955.8 2060.04
  4964.9 2056.09  4970.8 2053.33  4976.8 2052.12  4983.6 2049.66  4983.9 2049.16
  4988.1 2049.66  5009.7 2052.51  5022.5 2055.58  5040.6 2057.50  5063.8 2057.94
  5088.2 2063.32  5105.0 2069.44  5133.3 2078.34  5146.2 2083.38  5154.0 2088.86
  5164.3 2093.73  5174.6 2096.59  5182.3 2096.94  5195.2 2099.63  5205.5 2100.81
#Mann=6,-1,0
  4819.1     0.1       0  4870.2    0.07       0  4964.9     0.1       0
  4983.6    0.05       0  4988.1     0.1       0  5088.2     0.1       0
Bank Sta=4983.6,4988.1
Exp/Cntr=0.3,0.1

Type RM Length L Ch R = 1,3339,437,437,437
BEGIN DESCRIPTION:
Stream0269 7.0
END DESCRIPTION:
XS GIS Cut Line= 3
      1818575.00     13905024.99      1818625.00     13904775.00
      1818674.98     13904675.04
#Sta/Elev= 30
  4757.5 2086.53  4770.0 2085.05  4788.1 2083.33  4808.5 2078.83  4818.7 2075.45
  4828.9 2073.47  4839.1 2066.73  4849.3 2062.74  4890.1 2051.31  4930.9 2049.61
  4951.2 2050.36  4961.4 2049.22  4971.6 2046.17  4989.7 2044.04  4990.1 2043.54
  4994.0 2043.54  4994.3 2044.04  5002.2 2047.78  5009.9 2054.57  5015.2 2054.57
  5020.8 2057.86  5026.4 2058.30  5043.2 2062.73  5065.5 2066.99  5071.1 2067.05
  5087.9 2072.20  5093.5 2072.86  5101.9 2074.91  5110.3 2078.25  5124.2 2079.28
#Mann=4,-1,0
  4757.5    0.07       0  4770.0     0.1       0  4989.7    0.05       0
  4994.3     0.1       0
Bank Sta=4989.7,4994.3
Exp/Cntr=0.3,0.1

Type RM Length L Ch R = 1,2902,467,467,467
BEGIN DESCRIPTION:
Stream0269 6.0
END DESCRIPTION:
XS GIS Cut Line= 3
      1818925.01     13905124.98      1818975.00     13904975.00
      1818975.00     13904675.00
#Sta/Elev= 30
  4842.0 2084.46  4844.6 2084.46  4852.5 2082.98  4873.6 2078.24  4884.1 2075.50
  4894.7 2071.74  4915.8 2065.82  4936.8 2062.30  4947.4 2059.27  4979.0 2040.81
  4987.3 2039.91  4987.6 2039.41  4991.5 2039.41  4991.9 2039.91  4997.5 2041.20
  5020.1 2042.54  5030.1 2044.17  5050.1 2044.86  5070.1 2047.14  5120.1 2051.05
  5140.1 2053.77  5160.1 2057.68  5170.1 2060.62  5180.1 2062.52  5190.1 2065.25
  5216.6 2070.18  5230.1 2073.27  5240.1 2076.59  5270.1 2084.36  5300.1 2088.25
#Mann=4,-1,0
  4842.0    0.07       0  4987.3    0.05       0  4991.9    0.07       0
  5216.6     0.1       0
Bank Sta=4987.3,4991.9
Exp/Cntr=0.3,0.1

Type RM Length L Ch R = 1,2435,450,450,450
BEGIN DESCRIPTION:
Stream0269 5.0
END DESCRIPTION:
XS GIS Cut Line= 3
      1819425.00     13905024.99      1819425.00     13904925.00
      1819425.00     13904824.99
#Sta/Elev= 28
  4900.0 2050.44  4902.5 2050.44  4910.0 2048.67  4920.0 2046.50  4930.0 2044.65
  4940.0 2042.83  4950.0 2040.88  4960.0 2038.21  4970.0 2036.50  4980.0 2035.06
  4990.0 2031.85  4995.1 2029.46  4995.5 2028.96  4999.5 2028.96  4999.8 2029.46
  5000.0 2029.46  5002.5 2029.46  5010.0 2030.41  5020.0 2033.71  5030.0 2035.04
  5040.0 2038.65  5050.0 2044.85  5060.0 2047.45  5070.0 2049.12  5080.0 2050.21
  5090.0 2051.39  5097.5 2052.82  5100.0 2052.82
#Mann=3,-1,0
  4900.0    0.07       0  4995.1    0.05       0  4999.8    0.07       0
Bank Sta=4995.1,4999.8
Exp/Cntr=0.3,0.1

Type RM Length L Ch R = 1,1985,500,500,500
BEGIN DESCRIPTION:
Stream0269 4.0
END DESCRIPTION:
XS GIS Cut Line= 3
      1819975.00     13905274.99      1819875.00     13904925.00
      1819825.00     13904825.00
#Sta/Elev= 30
  4636.0 2092.46  4652.9 2089.86  4691.9 2085.74  4708.8 2081.24  4719.2 2077.79
  4725.7 2074.64  4730.9 2074.70  4759.5 2067.91  4781.6 2064.76  4798.5 2061.20
  4803.7 2061.17  4837.5 2056.71  4844.0 2054.52  4871.3 2048.25  4876.5 2048.19
  4927.2 2040.03  4937.6 2037.98  4944.1 2033.65  4949.3 2033.75  4959.1 2029.98
  4977.9 2028.21  4995.0 2028.16  4995.3 2027.66  4999.8 2028.16  5022.4 2029.76
  5030.7 2032.68  5036.3 2032.81  5044.7 2036.99  5053.1 2039.74  5111.8 2047.21
#Mann=4,-1,0
  4636.0     0.1       0  4959.1    0.07       0  4995.0    0.05       0
  4999.8    0.07       0
Bank Sta=4995,4999.8
Exp/Cntr=0.3,0.1

Type RM Length L Ch R = 1,1485,466,466,466
BEGIN DESCRIPTION:
Stream0269 3.0
END DESCRIPTION:
XS GIS Cut Line= 3
      1820275.01     13905274.98      1820375.00     13904925.00
      1820375.00     13904824.98
#Sta/Elev= 30
  4636.0 2091.47  4646.4 2090.16  4652.9 2088.43  4658.1 2088.24  4691.9 2078.18
  4698.4 2074.12  4725.7 2067.47  4730.9 2067.34  4759.5 2061.55  4764.7 2061.27
  4771.2 2059.34  4781.6 2058.08  4844.0 2045.73  4871.3 2041.41  4910.3 2037.26
  4916.8 2035.04  4949.3 2029.01  4968.8 2023.01  4977.9 2021.15  4988.3 2020.27
  4994.9 2019.15  4995.2 2018.65  4999.9 2019.15  5010.0 2019.79  5020.0 2024.36
  5030.0 2031.91  5040.0 2037.18  5050.0 2039.55  5090.0 2043.89  5100.0 2046.09
#Mann=4,-1,0
  4636.0     0.1       0  4988.3    0.07       0  4994.9    0.05       0
  4999.9    0.07       0
Bank Sta=4994.9,4999.9
Exp/Cntr=0.3,0.1

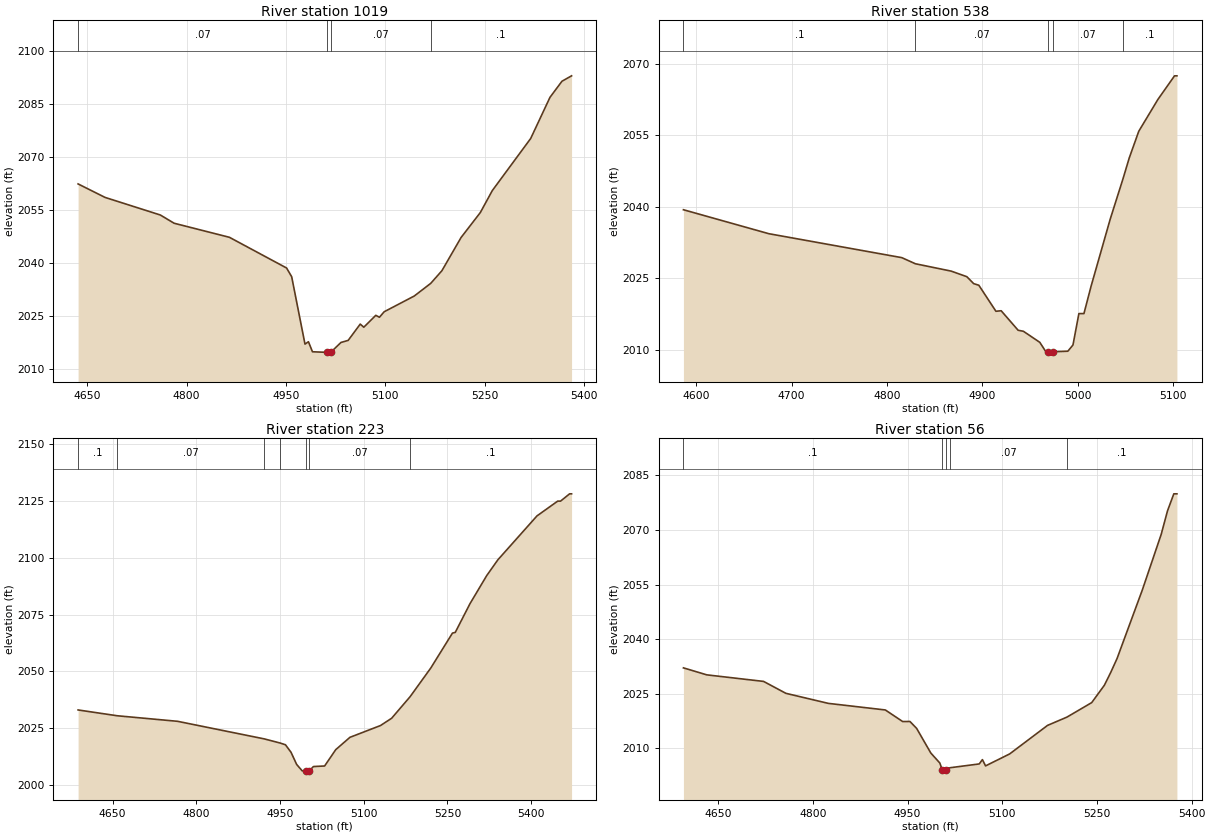
Type RM Length L Ch R = 1,1019,481,481,481
BEGIN DESCRIPTION:
Stream0269 2.0
END DESCRIPTION:
XS GIS Cut Line= 3
      1820719.77     13905323.77      1820825.00     13904975.00
      1820975.00     13904624.99
#Sta/Elev= 30
  4636.1 2062.48  4676.7 2058.67  4760.2 2053.69  4781.1 2051.35  4864.6 2047.37
  4950.9 2038.68  4958.6 2036.21  4978.7 2017.13  4983.9 2017.81  4990.0 2014.97
  5012.4 2014.80  5012.8 2014.30  5017.5 2014.80  5033.0 2017.60  5043.9 2018.19
  5062.1 2022.80  5067.5 2021.92  5085.6 2025.28  5091.1 2024.74  5098.3 2026.30
  5143.7 2030.75  5168.6 2034.34  5185.4 2037.91  5214.4 2047.32  5243.4 2054.37
  5261.5 2060.59  5319.5 2075.35  5348.6 2086.99  5366.7 2091.55  5381.2 2093.08
#Mann=4,-1,0
  4636.1    0.07       0  5012.4    0.05       0  5017.5    0.07       0
  5168.6     0.1       0
Bank Sta=5012.4,5017.5
Exp/Cntr=0.3,0.1

Type RM Length L Ch R = 1,538,315,315,315
BEGIN DESCRIPTION:
Stream0269 1.0
END DESCRIPTION:
XS GIS Cut Line= 3
      1821106.32     13905256.86      1821275.00     13904875.00
      1821275.00     13904774.96
#Sta/Elev= 30
  4586.6 2039.40  4676.1 2034.37  4815.6 2029.34  4829.8 2028.06  4867.4 2026.51
  4883.8 2025.34  4891.0 2023.88  4896.4 2023.54  4914.3 2018.08  4919.8 2018.19
  4937.6 2014.09  4943.1 2013.88  4960.3 2011.56  4966.4 2009.67  4969.3 2009.58
  4969.7 2009.08  4974.0 2009.08  4974.4 2009.58  4989.7 2009.69  4995.1 2011.00
  5001.3 2017.59  5006.6 2017.59  5014.1 2023.35  5034.1 2037.39  5047.7 2045.99
  5054.1 2050.27  5064.1 2055.88  5084.1 2062.54  5101.6 2067.52  5104.1 2067.52
#Mann=5,-1,0
  4586.6     0.1       0  4829.8    0.07       0  4969.3    0.05       0
  4974.4    0.07       0  5047.7     0.1       0
Bank Sta=4969.3,4974.4
Exp/Cntr=0.3,0.1

Type RM Length L Ch R = 1,223,167,167,167
BEGIN DESCRIPTION:
Stream0269 0.0
END DESCRIPTION:
XS GIS Cut Line= 3
      1821207.98     13905209.27      1821532.39     13905091.32
      1821561.21     13904553.09
#Sta/Elev= 30
  4588.3 2033.02  4658.2 2030.47  4766.6 2028.02  4921.7 2020.30  4950.0 2018.49
  4959.9 2017.70  4969.9 2014.37  4979.9 2009.06  4989.9 2006.22  4997.4 2006.17
  4997.7 2005.67  5002.5 2006.17  5009.9 2008.12  5030.0 2008.37  5050.0 2015.57
  5075.4 2020.98  5130.1 2026.16  5150.1 2029.36  5183.3 2038.89  5220.2 2051.45
  5259.1 2066.83  5264.1 2067.13  5290.3 2079.68  5320.4 2092.10  5340.4 2099.05
  5410.5 2118.37  5447.7 2124.89  5452.7 2124.87  5469.0 2128.09  5472.5 2128.09
#Mann=7,-1,0
  4588.3     0.1       0  4658.2    0.07       0  4921.7     0.1       0
  4950.0    0.07       0  4997.4    0.05       0  5002.5    0.07       0
  5183.3     0.1       0
Bank Sta=4997.4,5002.5
Exp/Cntr=0.3,0.1

Type RM Length L Ch R = 1,56,0,0,0
BEGIN DESCRIPTION:
Stream0269 0.1
END DESCRIPTION:
XS GIS Cut Line= 4
      1821343.52     13905295.54      1821658.60     13905123.68
      1821719.80     13905036.44      1821726.30     13904720.08
#Sta/Elev= 30
  4594.8 2032.11  4631.8 2030.19  4721.8 2028.39  4757.1 2025.12  4824.3 2022.36
  4914.7 2020.55  4942.2 2017.37  4953.7 2017.39  4964.3 2015.49  4986.8 2008.72
  5001.0 2005.99  5005.2 2003.98  5005.5 2003.48  5010.3 2003.98  5017.0 2004.68
  5063.5 2005.73  5068.5 2006.92  5073.5 2005.19  5111.7 2008.48  5171.7 2016.31
  5202.5 2018.59  5241.7 2022.57  5261.8 2027.35  5271.8 2030.84  5281.8 2034.65
  5321.8 2053.45  5351.8 2068.77  5361.8 2075.23  5371.8 2079.90  5376.7 2079.90
#Mann=5,-1,0
  4594.8     0.1       0  5005.2    0.05       0  5010.3     0.1       0
  5017.0    0.07       0  5202.5     0.1       0
Bank Sta=5005.2,5010.3
Exp/Cntr=0.3,0.1

Chan Stop Cuts=-1