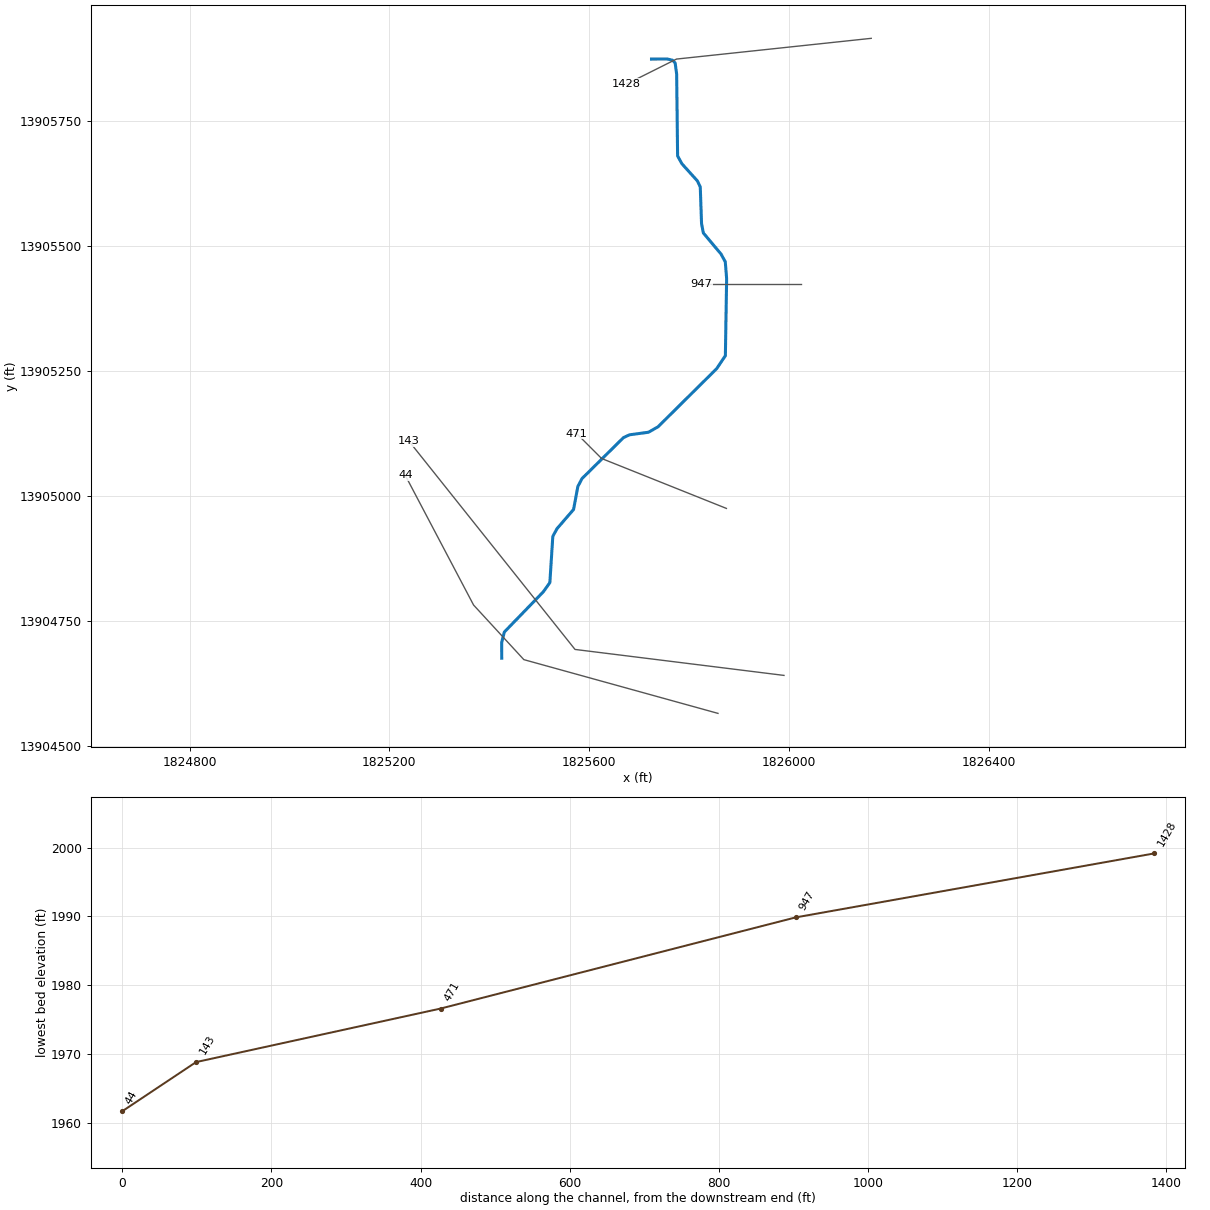
--- Stream0271.prj (project) ---

Proj Title=Stream0271 Base Level Engineering
Current Plan=p01
Default Exp/Contr=0.3,0.1
English Units
Geom File=g01
Flow File=f01
Plan File=p01
Y Axis Title=Elevation
X Axis Title(PF)=Main Channel Distance
X Axis Title(XS)=Station
BEGIN DESCRIPTION:
Stream0271
END DESCRIPTION:
DSS Export Rating Curves= 0
DSS Export Rating Curve Sorted= 0
DSS Export Volume Flow Curves= 0
DXF OffsetX= 0
DXF OffsetY= 0
DXF ScaleX= 1
DXF ScaleY= 10

--- Stream0271.p01 (plan) ---

Plan Title=Multiple Run
Short Identifier=Multiple
Geom File=g01
Flow File=f01
Subcritical Flow
K Sum by GR= 0
Std Step Tol= 0.01
Critical Tol= 0.01
Num of Std Step Trials= 20
Max Error Tol= 0.3
Flow Tol Ratio= 0.001
Split Flow NTrial= 30
Split Flow Tol= 0.02
Split Flow Ratio= 0.02
Log Output Level= 0
Friction Slope Method= 1
Unsteady Friction Slope Method= 2
Unsteady Bridges Friction Slope Method= 1
Parabolic Critical Depth
Global Vel Dist=  1 , 1 , 1
Global Log Level= 0
CheckData=True
Encroach Param= -1, 0, 0, 0
BEGIN DESCRIPTION:
Multiple Run
END DESCRIPTION:

--- Stream0271.f01 (steady flow) ---

Flow Title=Multiple
Program Version=4.10
Number of Profiles= 7
Profile Names=10-year,25-year,50-year,1pct_min,100-year,1pct_plu,500-year
River Rch & RM=Stream0271,Reach-1         ,1428
     910    1557    2174    1471    2935    5856    5281
Boundary for River Rch & Prof#=Stream0271,Reach-1         , 1
Up Type= 0
Dn Type= 3
Dn Slope=0.005
Boundary for River Rch & Prof#=Stream0271,Reach-1         , 2
Up Type= 0
Dn Type= 3
Dn Slope=0.005
Boundary for River Rch & Prof#=Stream0271,Reach-1         , 3
Up Type= 0
Dn Type= 3
Dn Slope=0.005
Boundary for River Rch & Prof#=Stream0271,Reach-1         , 4
Up Type= 0
Dn Type= 3
Dn Slope=0.005
Boundary for River Rch & Prof#=Stream0271,Reach-1         , 5
Up Type= 0
Dn Type= 3
Dn Slope=0.005
Boundary for River Rch & Prof#=Stream0271,Reach-1         , 6
Up Type= 0
Dn Type= 3
Dn Slope=0.005
Boundary for River Rch & Prof#=Stream0271,Reach-1         , 7
Up Type= 0
Dn Type= 3
Dn Slope=0.005
DSS Import GetInterval= 0
DSS Import GetPeak= 0
DSS Import FillOption= 0

--- Stream0271.g01 (geometry) ---

Geom Title=Existing Conditions

River Reach=Stream0271,Reach-1
Reach XY= 30
      1825725.00     13905875.00      1825756.95     13905875.11
      1825767.18     13905872.63      1825772.30     13905867.30
      1825775.35     13905845.36      1825777.26     13905680.94
      1825785.85     13905665.35      1825816.81     13905631.03
      1825822.64     13905619.02      1825825.24     13905545.10
      1825828.86     13905526.60      1825864.15     13905484.65
      1825872.74     13905469.06      1825875.46     13905435.18
      1825872.94     13905280.85      1825855.40     13905254.83
      1825738.21     13905138.63      1825718.95     13905127.54
      1825681.04     13905122.47      1825668.93     13905116.85
      1825585.75     13905034.71      1825577.49     13905018.98
      1825568.86     13904972.83      1825535.84     13904934.65
      1825527.33     13904919.03      1825521.39     13904826.50
      1825508.54     13904808.25      1825430.33     13904727.51
      1825424.93     13904706.88      1825425.00     13904675.00

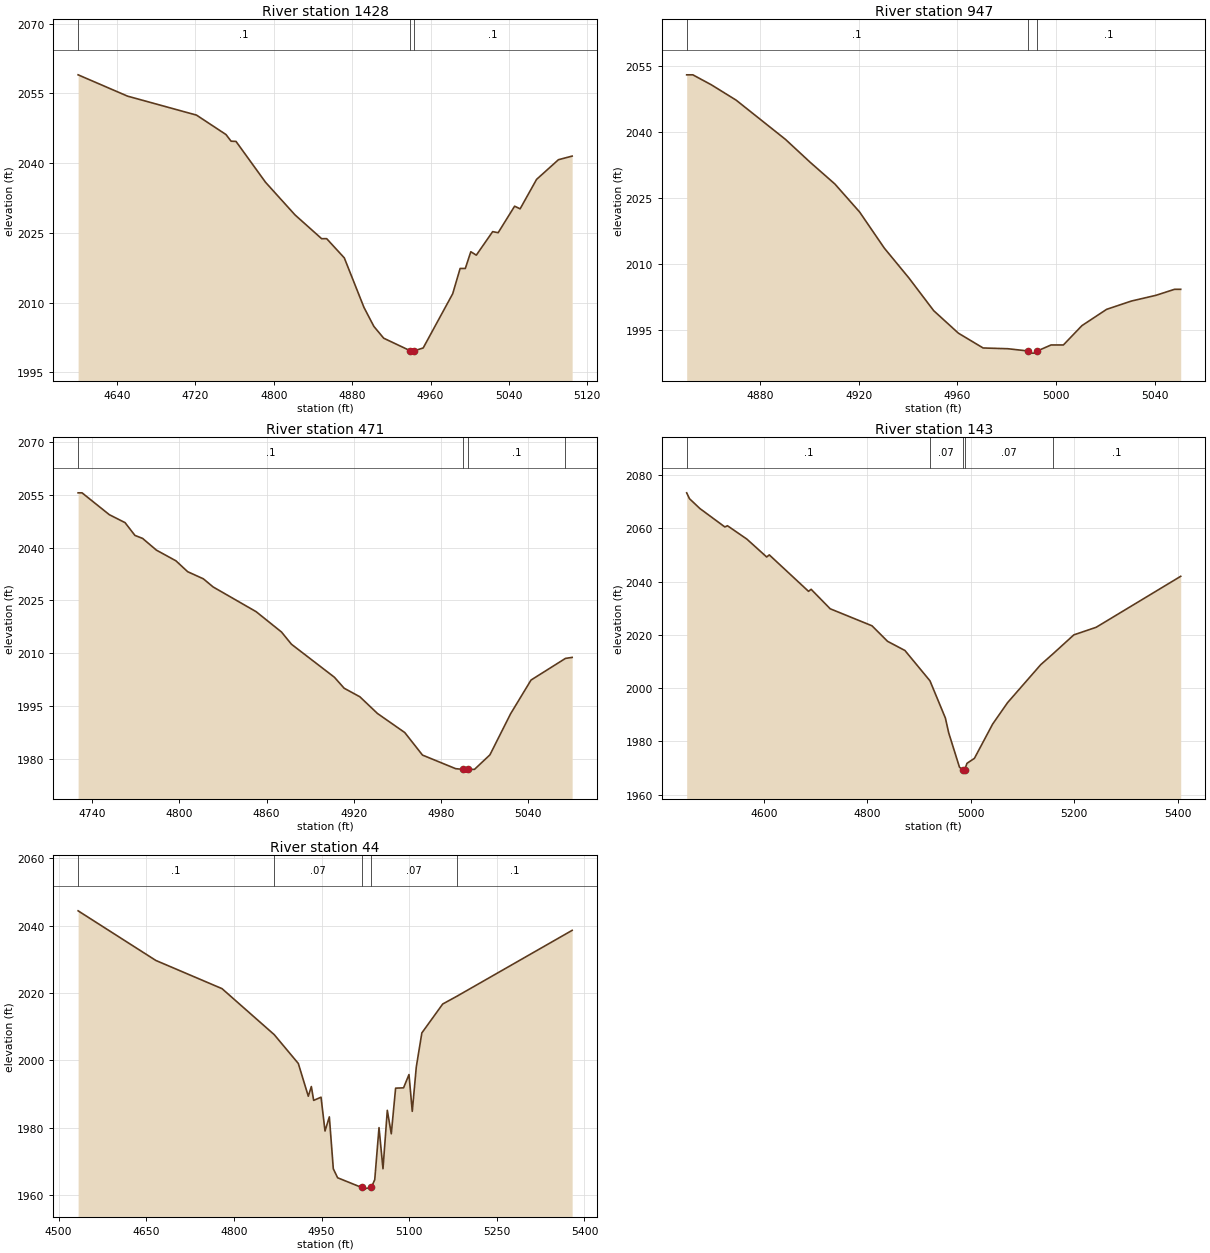
Type RM Length L Ch R = 1,1428,481,481,481
BEGIN DESCRIPTION:
Stream0271 3.0
END DESCRIPTION:
XS GIS Cut Line= 3
      1826165.08     13905916.53      1825775.00     13905875.00
      1825674.99     13905824.99
#Sta/Elev= 30
  4600.4 2058.99  4650.8 2054.41  4721.2 2050.33  4751.3 2046.15  4756.5 2044.72
  4761.5 2044.68  4791.6 2035.90  4821.7 2028.88  4848.9 2023.76  4854.0 2023.77
  4872.0 2019.64  4892.1 2008.98  4902.2 2004.90  4912.2 2002.37  4939.4 1999.66
  4939.7 1999.16  4943.4 1999.66  4952.5 2000.27  4982.6 2011.92  4990.2 2017.36
  4995.5 2017.36  5001.1 2020.96  5006.7 2020.22  5023.4 2025.28  5029.0 2025.05
  5045.8 2030.75  5051.4 2030.18  5068.2 2036.51  5090.5 2040.74  5104.5 2041.52
#Mann=3,-1,0
  4600.4     0.1       0  4939.4    0.05       0  4943.4     0.1       0
Bank Sta=4939.4,4943.4
Exp/Cntr=0.3,0.1

Type RM Length L Ch R = 1,947,476,476,476
BEGIN DESCRIPTION:
Stream0271 2.0
END DESCRIPTION:
XS GIS Cut Line= 3
      1826024.99     13905425.00      1825875.00     13905425.00
      1825824.99     13905425.00
#Sta/Elev= 27
  4850.4 2053.05  4852.9 2053.05  4860.4 2050.78  4870.4 2047.31  4890.4 2038.39
  4900.4 2033.19  4910.4 2028.26  4920.4 2021.91  4930.4 2013.71  4940.4 2006.90
  4950.4 1999.50  4960.4 1994.39  4970.4 1991.03  4980.4 1990.86  4988.4 1990.36
  4988.6 1989.86  4992.1 1989.86  4992.4 1990.36  4997.9 1991.71  5000.4 1991.71
  5002.9 1991.71  5010.4 1996.10  5020.4 1999.80  5030.4 2001.68  5040.4 2002.99
  5047.9 2004.35  5050.4 2004.35
#Mann=3,-1,0
  4850.4     0.1       0  4988.4    0.05       0  4992.4     0.1       0
Bank Sta=4988.4,4992.4
Exp/Cntr=0.3,0.1

Type RM Length L Ch R = 1,471,328,328,328
BEGIN DESCRIPTION:
Stream0271 1.0
END DESCRIPTION:
XS GIS Cut Line= 3
      1825875.01     13904975.00      1825625.00     13905075.00
      1825574.98     13905125.02
#Sta/Elev= 30
  4730.3 2055.52  4733.0 2055.52  4751.8 2049.32  4762.6 2047.07  4769.4 2043.45
  4774.7 2042.59  4784.2 2039.27  4797.6 2036.25  4805.7 2033.16  4816.5 2031.14
  4823.2 2028.84  4852.8 2021.83  4870.3 2016.05  4877.1 2012.60  4906.7 2003.23
  4913.4 2000.12  4924.2 1997.70  4936.3 1992.97  4955.1 1987.56  4967.3 1981.17
  4990.1 1977.32  4994.9 1977.12  4995.1 1976.62  4998.9 1977.12  5003.1 1977.12
  5013.7 1981.23  5027.9 1992.85  5042.0 2002.44  5065.7 2008.58  5070.3 2008.86
#Mann=4,-1,0
  4730.3     0.1       0  4994.9    0.05       0  4998.9     0.1       0
  5065.7    0.07       0
Bank Sta=4994.9,4998.9
Exp/Cntr=0.3,0.1

Type RM Length L Ch R = 1,143,99,99,99
BEGIN DESCRIPTION:
Stream0271 0.0
END DESCRIPTION:
XS GIS Cut Line= 3
      1825990.33     13904640.54      1825571.79     13904692.55
      1825239.53     13905109.37
#Sta/Elev= 30
  4451.1 2073.36  4456.5 2071.16  4476.6 2067.47  4524.9 2060.54  4529.9 2061.00
  4567.3 2056.00  4605.7 2049.27  4610.8 2050.05  4686.6 2036.36  4691.6 2037.13
  4728.5 2029.81  4809.2 2023.43  4839.4 2017.58  4872.9 2014.15  4921.3 2002.76
  4951.1 1988.77  4957.5 1983.23  4978.3 1970.33  4984.4 1969.34  4984.6 1968.84
  4988.4 1969.34  4992.8 1971.77  5007.2 1973.64  5042.4 1986.50  5071.2 1994.54
  5135.3 2008.81  5159.4 2012.95  5199.3 2020.01  5242.6 2022.87  5405.9 2042.01
#Mann=5,-1,0
  4451.1     0.1       0  4921.3    0.07       0  4984.4    0.05       0
  4988.4    0.07       0  5159.4     0.1       0
Bank Sta=4984.4,4988.4
Exp/Cntr=0.3,0.1

Type RM Length L Ch R = 1,44,0,0,0
BEGIN DESCRIPTION:
Stream0271 0.1
END DESCRIPTION:
XS GIS Cut Line= 4
      1825858.16     13904564.49      1825469.31     13904672.12
      1825368.61     13904781.50      1825231.96     13905040.97
#Sta/Elev= 30
  4533.5 2044.37  4666.5 2029.63  4779.8 2021.25  4869.1 2007.59  4910.3 1999.03
  4927.4 1989.30  4932.6 1992.17  4936.6 1988.06  4949.2 1989.01  4956.0 1978.96
  4963.4 1983.17  4970.2 1967.74  4977.6 1965.07  5018.6 1962.20  5019.1 1961.70
  5035.2 1962.20  5041.1 1964.50  5048.4 1979.97  5055.2 1967.76  5062.6 1985.11
  5069.4 1978.13  5076.8 1991.69  5090.4 1991.79  5099.7 1995.73  5105.3 1984.81
  5112.2 1997.99  5121.7 2008.10  5157.4 2016.69  5181.2 2018.95  5378.9 2038.57
#Mann=5,-1,0
  4533.5     0.1       0  4869.1    0.07       0  5018.6    0.05       0
  5035.2    0.07       0  5181.2     0.1       0
Bank Sta=5018.6,5035.2
Exp/Cntr=0.3,0.1

Chan Stop Cuts=-1