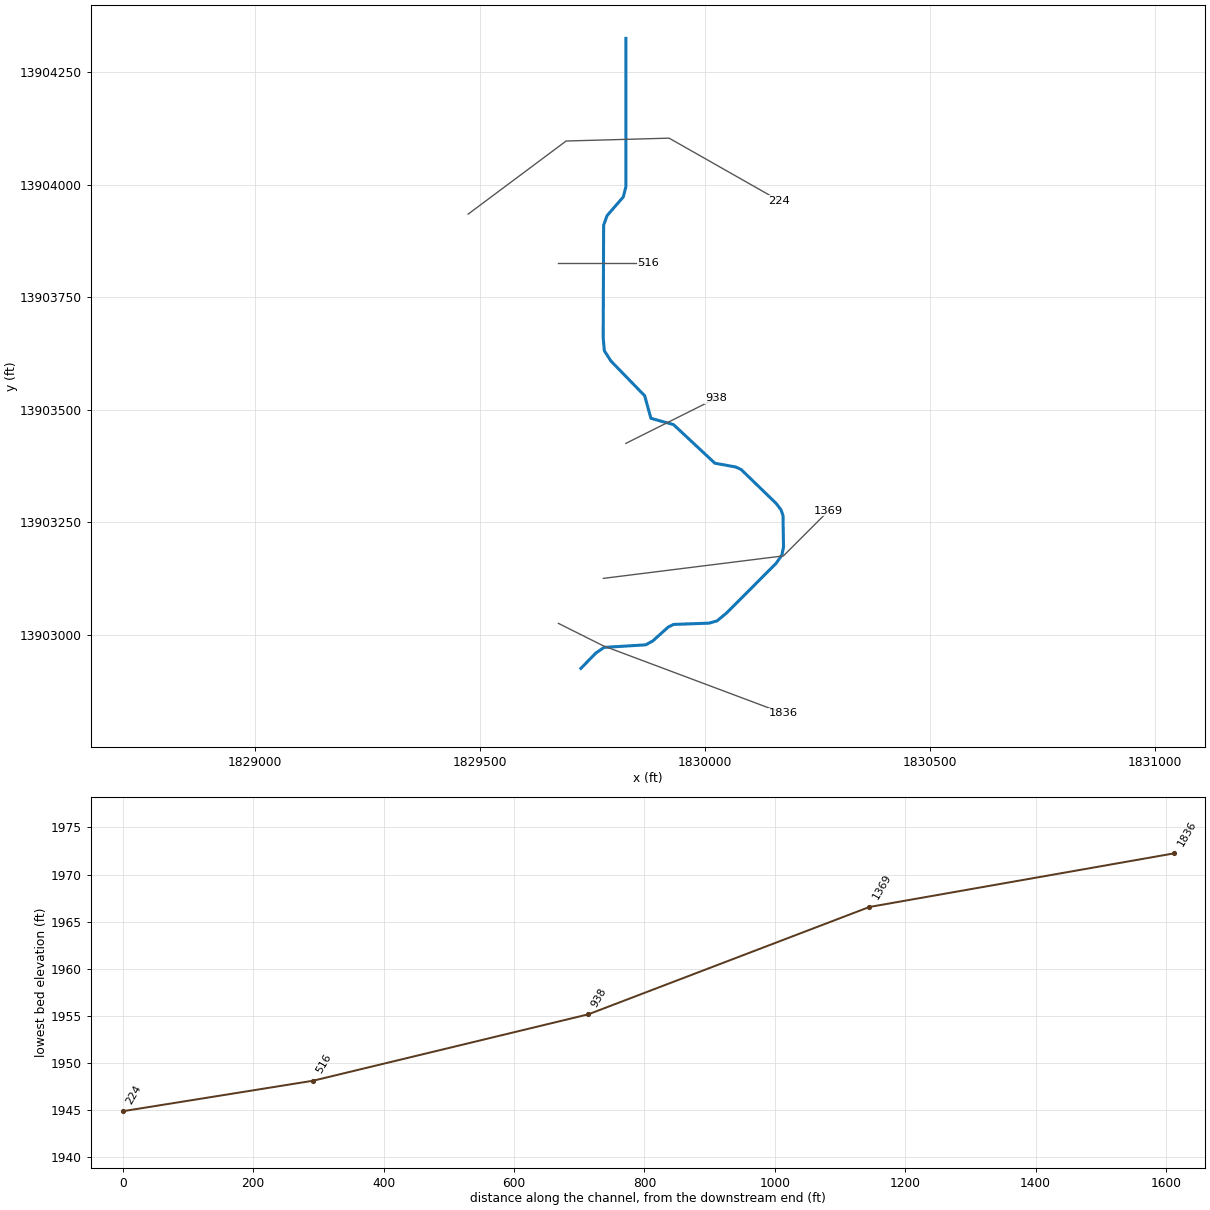
--- Stream0272.prj (project) ---

Proj Title=Stream0272 Base Level Engineering
Current Plan=p01
Default Exp/Contr=0.3,0.1
English Units
Geom File=g01
Flow File=f01
Plan File=p01
BEGIN DESCRIPTION:
Stream0272
END DESCRIPTION:

--- Stream0272.p01 (plan) ---

Plan Title=Multiple Run
Short Identifier=Multiple
Geom File=g01
Flow File=f01
Subcritical Flow
K Sum by GR= 0
Std Step Tol= 0.01
Critical Tol= 0.01
Num of Std Step Trials= 20
Max Error Tol= 0.3
Flow Tol Ratio= 0.001
Split Flow NTrial= 30
Split Flow Tol= 0.02
Split Flow Ratio= 0.02
Log Output Level= 0
Friction Slope Method= 1
Unsteady Friction Slope Method= 2
Unsteady Bridges Friction Slope Method= 1
Parabolic Critical Depth
Global Vel Dist=  1 , 1 , 1
Global Log Level= 0
CheckData=True
Encroach Param= -1, 0, 0, 0
BEGIN DESCRIPTION:
Multiple Run
END DESCRIPTION:

--- Stream0272.f01 (steady flow) ---

Flow Title=Multiple
Number of Profiles=7
Profile Names=10-year,25-year,50-year,1pct_min,100-year,1pct_plu,500-year
River Rch & RM= Stream0272,Reach-1,1836
    1450    2533    3586    2452    4893    9763    9011
Boundary for River Rch & Prof#=Stream0272,Reach-1,1
Up Type=0
Dn Type=3
Dn Slope=0.005
Boundary for River Rch & Prof#=Stream0272,Reach-1,2
Up Type=0
Dn Type=3
Dn Slope=0.005
Boundary for River Rch & Prof#=Stream0272,Reach-1,3
Up Type=0
Dn Type=3
Dn Slope=0.005
Boundary for River Rch & Prof#=Stream0272,Reach-1,4
Up Type=0
Dn Type=3
Dn Slope=0.005
Boundary for River Rch & Prof#=Stream0272,Reach-1,5
Up Type=0
Dn Type=3
Dn Slope=0.005
Boundary for River Rch & Prof#=Stream0272,Reach-1,6
Up Type=0
Dn Type=3
Dn Slope=0.005
Boundary for River Rch & Prof#=Stream0272,Reach-1,7
Up Type=0
Dn Type=3
Dn Slope=0.005

--- Stream0272.g01 (geometry) ---

Geom Title=Existing Conditions

River Reach=Stream0272,Reach-1
Reach XY= 30
      1829725.00     13902925.00      1829757.95     13902958.88
      1829776.40     13902971.61      1829869.04     13902977.32
      1829884.64     13902985.88      1829918.96     13903016.81
      1829930.98     13903022.64      1830009.78     13903025.52
      1830027.43     13903030.52      1830048.52     13903047.87
      1830158.60     13903158.25      1830171.54     13903176.50
      1830175.22     13903195.06      1830174.07     13903264.52
      1830169.61     13903277.44      1830158.61     13903291.79
      1830081.07     13903366.85      1830068.96     13903372.47
      1830022.72     13903380.87      1829930.74     13903466.70
      1829880.62     13903480.62      1829866.70     13903530.74
      1829791.46     13903608.25      1829777.06     13903630.85
      1829774.51     13903659.80      1829775.52     13903909.78
      1829783.14     13903931.06      1829819.25     13903972.67
      1829824.93     13903995.03      1829825.00     13904325.00

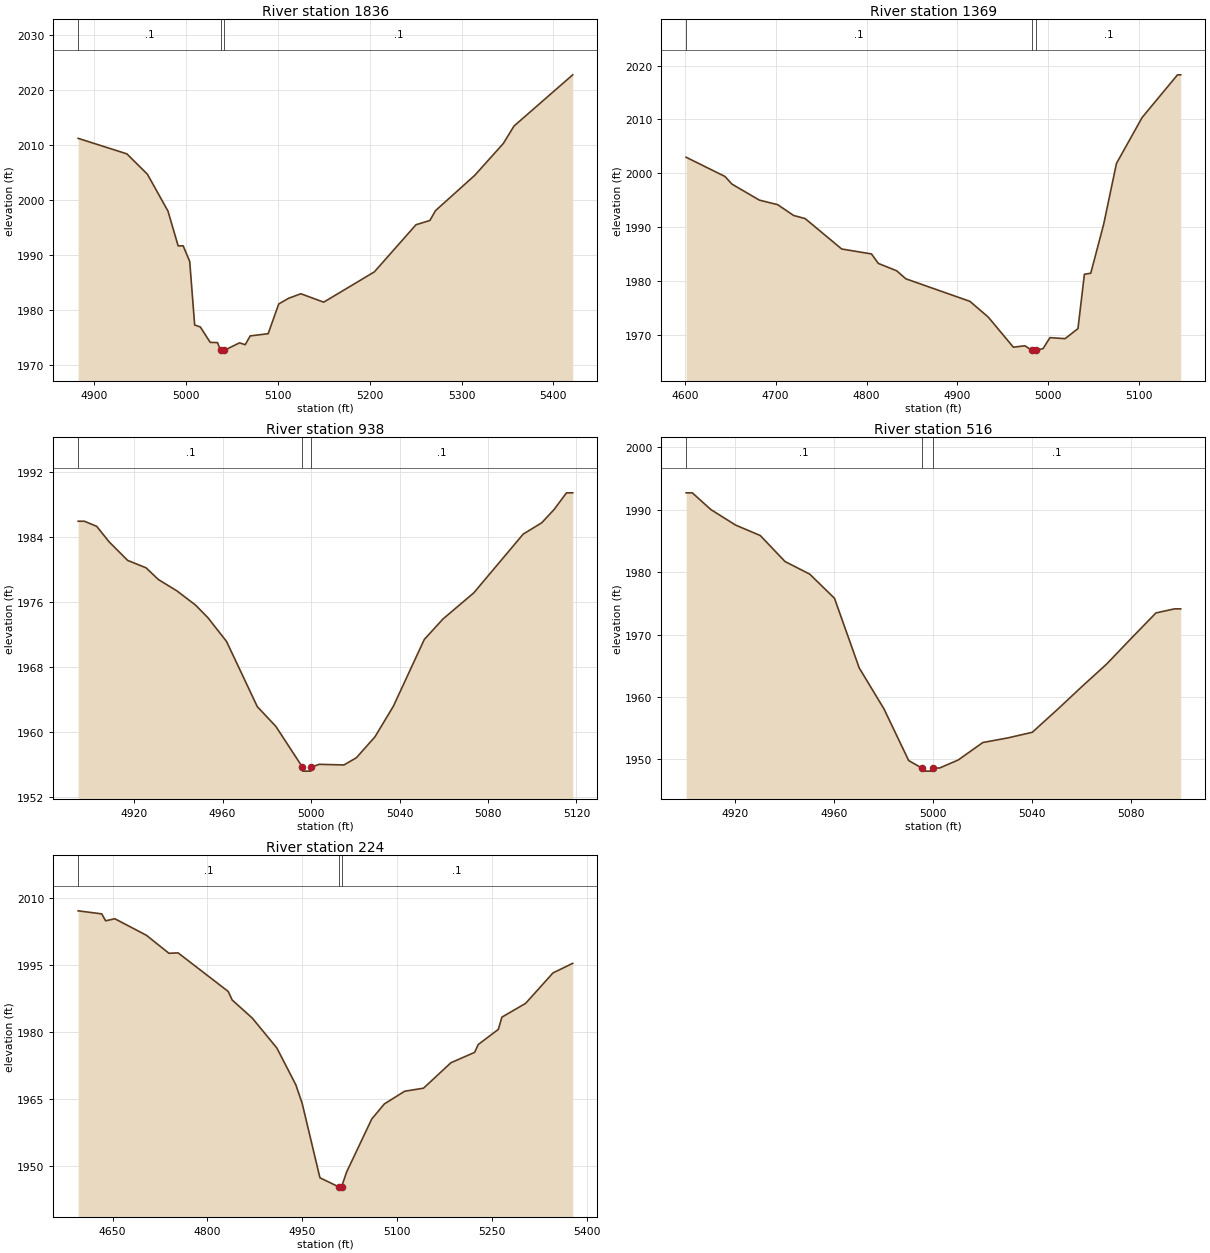
Type RM Length L Ch R = 1,1836,467,467,467
BEGIN DESCRIPTION:
Stream0272 4.0
END DESCRIPTION:
XS GIS Cut Line= 3
      1829674.97     13903025.02      1829775.00     13902975.00
      1830174.96     13902825.01
#Sta/Elev= 30
  4882.2 2011.27  4935.3 2008.45  4957.7 2004.75  4980.1 1998.05  4991.2 1991.73
  4996.7 1991.73  5003.8 1988.89  5009.2 1977.35  5015.4 1976.99  5026.1 1974.20
  5034.1 1974.15  5037.4 1972.74  5037.7 1972.24  5041.4 1972.74  5058.1 1974.11
  5064.3 1973.77  5069.7 1975.37  5089.3 1975.77  5100.8 1981.17  5111.5 1982.20
  5124.9 1983.03  5149.8 1981.50  5205.0 1987.00  5250.4 1995.57  5265.5 1996.34
  5271.7 1998.14  5314.4 2004.54  5345.6 2010.34  5357.2 2013.50  5421.2 2022.81
#Mann=3,-1,0
  4882.2     0.1       0  5037.4    0.05       0  5041.4     0.1       0
Bank Sta=5037.4,5041.4
Exp/Cntr=0.3,0.1

Type RM Length L Ch R = 1,1369,431,431,431
BEGIN DESCRIPTION:
Stream0272 3.0
END DESCRIPTION:
XS GIS Cut Line= 3
      1829775.01     13903125.00      1830175.00     13903175.00
      1830274.98     13903274.98
#Sta/Elev= 30
  4601.4 2002.97  4644.2 1999.39  4651.8 1997.98  4682.0 1995.00  4702.2 1994.15
  4719.8 1992.14  4732.4 1991.57  4772.7 1985.91  4805.5 1984.99  4813.0 1983.23
  4833.2 1981.86  4843.3 1980.37  4913.8 1976.18  4934.0 1973.26  4961.7 1967.65
  4974.3 1967.92  4982.3 1967.05  4982.6 1966.55  4986.4 1967.05  4994.4 1967.40
  5002.0 1969.43  5018.6 1969.24  5032.8 1971.11  5039.9 1981.21  5046.9 1981.41
  5061.1 1990.50  5075.2 2001.82  5103.5 2010.37  5142.4 2018.29  5145.9 2018.29
#Mann=3,-1,0
  4601.4     0.1       0  4982.3    0.05       0  4986.4     0.1       0
Bank Sta=4982.3,4986.4
Exp/Cntr=0.3,0.1

Type RM Length L Ch R = 1,938,422,422,422
BEGIN DESCRIPTION:
Stream0272 2.0
END DESCRIPTION:
XS GIS Cut Line= 3
      1829825.01     13903425.00      1829925.00     13903475.00
      1830025.00     13903525.00
#Sta/Elev= 30
  4894.7 1985.95  4897.5 1985.95  4903.1 1985.32  4908.7 1983.41  4917.1 1981.12
  4925.4 1980.21  4931.0 1978.76  4939.4 1977.36  4947.8 1975.61  4953.4 1974.05
  4961.8 1971.13  4975.7 1963.10  4984.1 1960.66  4996.1 1955.65  4996.3 1955.15
  4999.9 1955.15  5000.2 1955.65  5003.7 1955.99  5014.9 1955.91  5020.5 1956.80
  5028.9 1959.38  5037.2 1963.14  5051.2 1971.38  5059.6 1973.89  5073.6 1977.13
  5095.9 1984.36  5104.3 1985.76  5109.9 1987.40  5115.5 1989.45  5118.3 1989.45
#Mann=3,-1,0
  4894.7     0.1       0  4996.1    0.05       0  5000.2     0.1       0
Bank Sta=4996.1,5000.2
Exp/Cntr=0.3,0.1

Type RM Length L Ch R = 1,516,292,292,292
BEGIN DESCRIPTION:
Stream0272 1.0
END DESCRIPTION:
XS GIS Cut Line= 3
      1829675.01     13903825.00      1829775.00     13903825.00
      1829875.01     13903825.00
#Sta/Elev= 28
  4900.1 1992.73  4902.6 1992.73  4910.1 1990.05  4920.1 1987.56  4930.1 1985.88
  4940.1 1981.71  4950.1 1979.69  4960.1 1975.82  4970.1 1964.65  4980.1 1958.09
  4990.1 1949.80  4995.4 1948.60  4995.7 1948.10  4999.5 1948.10  4999.8 1948.60
  5000.1 1948.60  5002.6 1948.60  5010.1 1949.88  5020.1 1952.69  5030.1 1953.42
  5040.1 1954.33  5050.1 1957.93  5060.1 1961.64  5070.1 1965.25  5080.1 1969.39
  5090.1 1973.47  5097.6 1974.12  5100.1 1974.12
#Mann=3,-1,0
  4900.1     0.1       0  4995.4    0.05       0  4999.8     0.1       0
Bank Sta=4995.4,4999.8
Exp/Cntr=0.3,0.1

Type RM Length L Ch R = 1,224,0,0,0
BEGIN DESCRIPTION:
Stream0272 0.0
END DESCRIPTION:
XS GIS Cut Line= 4
      1829474.49     13903934.44      1829692.12     13904096.82
      1829920.94     13904103.21      1830166.15     13903964.03
#Sta/Elev= 30
  4595.5 2007.03  4632.8 2006.35  4639.0 2004.80  4653.6 2005.26  4703.7 2001.55
  4739.1 1997.55  4753.7 1997.63  4832.9 1989.02  4839.2 1987.11  4871.0 1983.07
  4909.9 1976.38  4939.9 1968.16  4949.9 1964.03  4978.0 1947.40  5007.8 1945.36
  5008.1 1944.86  5012.2 1945.36  5020.0 1948.61  5060.0 1960.53  5080.0 1963.90
  5112.1 1966.73  5141.9 1967.41  5185.2 1973.09  5222.7 1975.41  5228.4 1977.16
  5260.2 1980.54  5265.9 1983.28  5303.4 1986.36  5346.7 1993.16  5377.9 1995.30
#Mann=3,-1,0
  4595.5     0.1       0  5007.8    0.05       0  5012.2     0.1       0
Bank Sta=5007.8,5012.2
Exp/Cntr=0.3,0.1

Chan Stop Cuts=-1