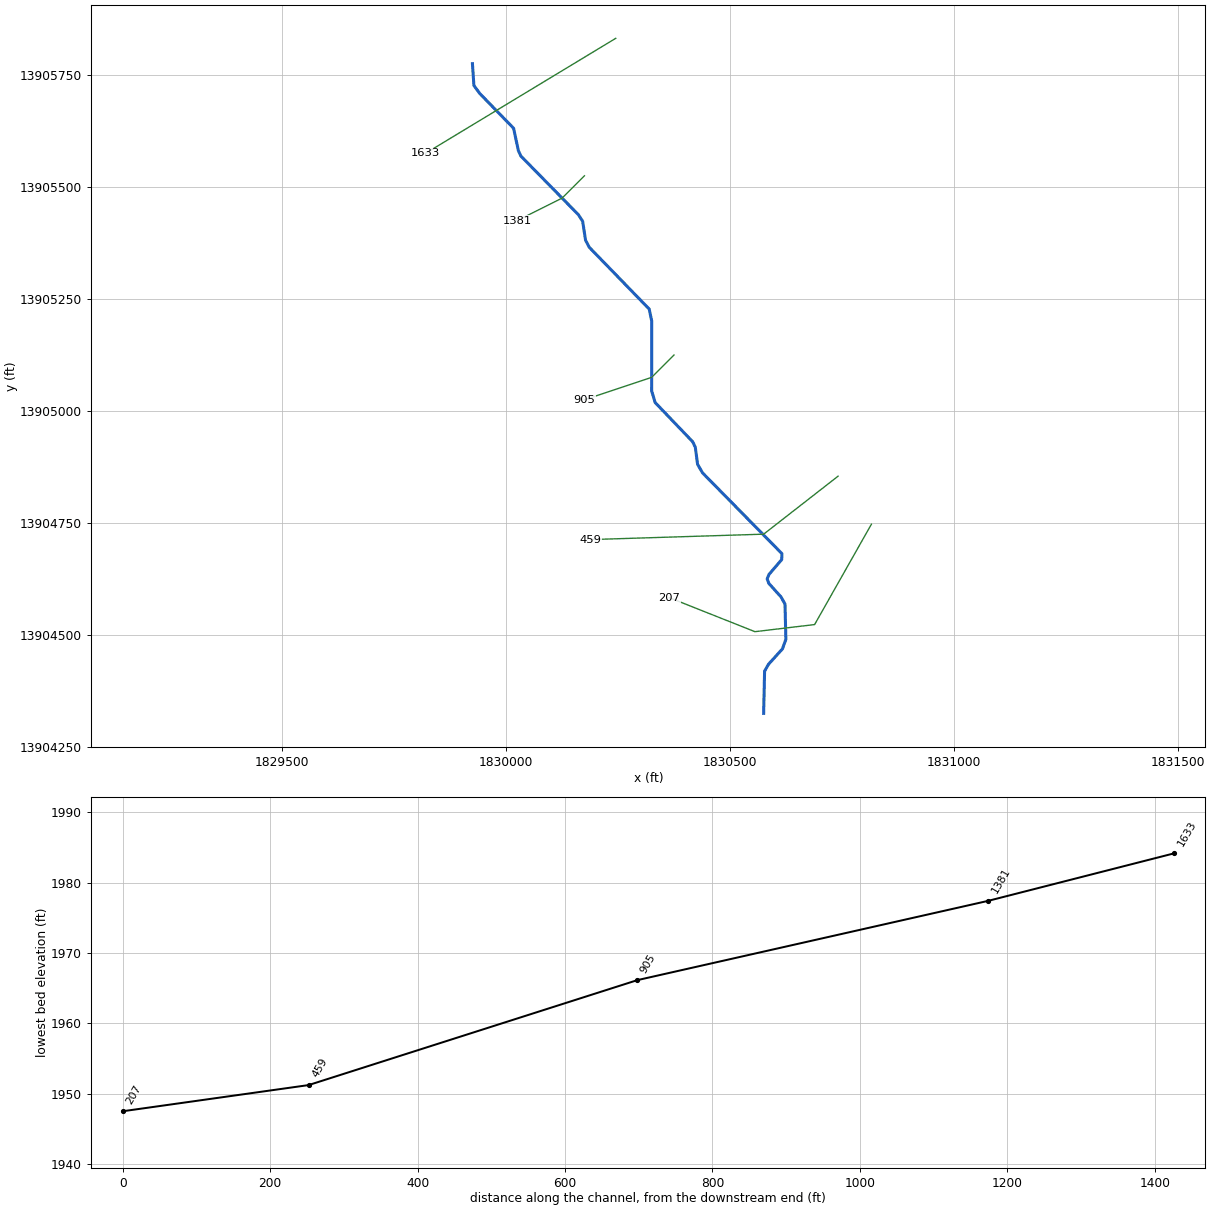
--- Stream0273.prj (project) ---

Proj Title=Stream0273 Base Level Engineering
Current Plan=p01
Default Exp/Contr=0.3,0.1
English Units
Geom File=g01
Flow File=f01
Plan File=p01
BEGIN DESCRIPTION:
Stream0273
END DESCRIPTION:

--- Stream0273.p01 (plan) ---

Plan Title=Multiple Run
Short Identifier=Multiple
Geom File=g01
Flow File=f01
Subcritical Flow
K Sum by GR= 0
Std Step Tol= 0.01
Critical Tol= 0.01
Num of Std Step Trials= 20
Max Error Tol= 0.3
Flow Tol Ratio= 0.001
Split Flow NTrial= 30
Split Flow Tol= 0.02
Split Flow Ratio= 0.02
Log Output Level= 0
Friction Slope Method= 1
Unsteady Friction Slope Method= 2
Unsteady Bridges Friction Slope Method= 1
Parabolic Critical Depth
Global Vel Dist=  1 , 1 , 1
Global Log Level= 0
CheckData=True
Encroach Param= -1, 0, 0, 0
BEGIN DESCRIPTION:
Multiple Run
END DESCRIPTION:

--- Stream0273.f01 (steady flow) ---

Flow Title=Multiple
Number of Profiles=7
Profile Names=10-year,25-year,50-year,1pct_min,100-year,1pct_plu,500-year
River Rch & RM= Stream0273,Reach-1,1633
     938    1604    2240    1515    3023    6032    5437
Boundary for River Rch & Prof#=Stream0273,Reach-1,1
Up Type=0
Dn Type=3
Dn Slope=0.005
Boundary for River Rch & Prof#=Stream0273,Reach-1,2
Up Type=0
Dn Type=3
Dn Slope=0.005
Boundary for River Rch & Prof#=Stream0273,Reach-1,3
Up Type=0
Dn Type=3
Dn Slope=0.005
Boundary for River Rch & Prof#=Stream0273,Reach-1,4
Up Type=0
Dn Type=3
Dn Slope=0.005
Boundary for River Rch & Prof#=Stream0273,Reach-1,5
Up Type=0
Dn Type=3
Dn Slope=0.005
Boundary for River Rch & Prof#=Stream0273,Reach-1,6
Up Type=0
Dn Type=3
Dn Slope=0.005
Boundary for River Rch & Prof#=Stream0273,Reach-1,7
Up Type=0
Dn Type=3
Dn Slope=0.005

--- Stream0273.g01 (geometry) ---

Geom Title=Existing Conditions

River Reach=Stream0273,Reach-1
Reach XY= 30
      1829925.00     13905775.00      1829928.29     13905726.36
      1829941.62     13905708.31      1830016.84     13905631.05
      1830027.53     13905581.05      1830033.16     13905568.95
      1830161.37     13905438.21      1830171.02     13905423.35
      1830177.54     13905381.05      1830185.78     13905365.32
      1830319.54     13905227.45      1830325.29     13905200.12
      1830324.96     13905044.98      1830332.83     13905018.81
      1830416.82     13904931.04      1830422.46     13904918.95
      1830427.53     13904881.05      1830438.63     13904861.79
      1830615.70     13904681.67      1830615.40     13904668.34
      1830586.85     13904635.06      1830582.81     13904625.10
      1830586.63     13904615.15      1830613.86     13904584.79
      1830622.65     13904569.11      1830624.63     13904490.27
      1830616.95     13904468.95      1830585.86     13904434.65
      1830577.11     13904419.13      1830575.00     13904325.00

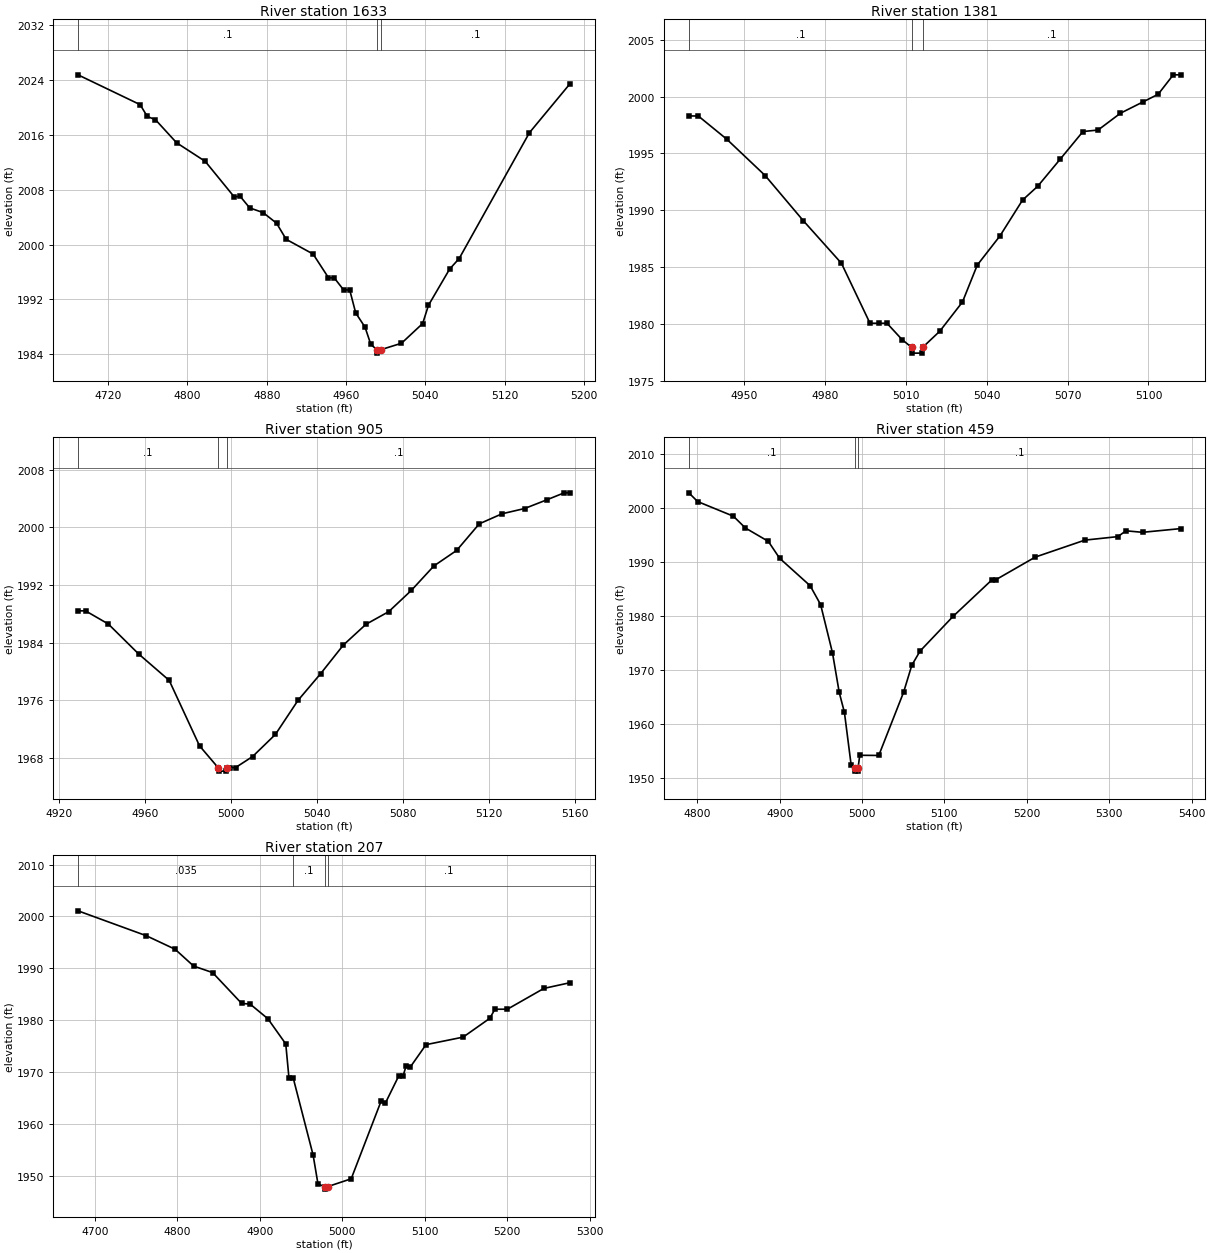
Type RM Length L Ch R = 1,1633,252,252,252
BEGIN DESCRIPTION:
Stream0273 4.0
END DESCRIPTION:
XS GIS Cut Line= 2
      1830244.84     13905831.71      1829819.88     13905574.77
#Sta/Elev= 30
  4689.5 2024.76  4752.2 2020.41  4759.4 2018.69  4767.7 2018.21  4789.0 2014.85
  4817.9 2012.14  4847.2 2006.95  4853.1 2007.05  4862.8 2005.35  4876.3 2004.67
  4889.9 2003.12  4899.6 2000.77  4926.8 1998.62  4942.3 1995.17  4948.2 1995.13
  4957.8 1993.35  4963.7 1993.41  4969.8 1990.03  4979.2 1987.96  4985.0 1985.46
  4991.1 1984.67  4991.4 1984.17  4995.1 1984.67  5016.0 1985.61  5037.4 1988.49
  5043.2 1991.14  5064.6 1996.43  5074.2 1997.96  5145.1 2016.31  5186.1 2023.46
#Mann=3,-1,0
  4689.5     0.1       0  4991.1    0.05       0  4995.1     0.1       0
Bank Sta=4991.1,4995.1
Exp/Cntr=0.3,0.1

Type RM Length L Ch R = 1,1381,476,476,476
BEGIN DESCRIPTION:
Stream0273 3.0
END DESCRIPTION:
XS GIS Cut Line= 3
      1830175.00     13905525.00      1830125.00     13905475.00
      1830025.01     13905425.00
#Sta/Elev= 28
  4929.5 1998.29  4933.0 1998.29  4943.6 1996.24  4957.8 1993.05  4971.9 1989.09
  4986.1 1985.33  4996.7 1980.05  5000.2 1980.05  5003.0 1980.05  5008.6 1978.61
  5012.2 1977.92  5012.4 1977.42  5015.9 1977.42  5016.2 1977.92  5022.6 1979.35
  5031.0 1981.92  5036.5 1985.17  5044.9 1987.73  5053.3 1990.89  5058.9 1992.10
  5067.3 1994.50  5075.7 1996.92  5081.3 1997.05  5089.6 1998.53  5098.0 1999.53
  5103.6 2000.20  5109.2 2001.91  5112.0 2001.91
#Mann=3,-1,0
  4929.5     0.1       0  5012.2    0.05       0  5016.2     0.1       0
Bank Sta=5012.2,5016.2
Exp/Cntr=0.3,0.1

Type RM Length L Ch R = 1,905,446,446,446
BEGIN DESCRIPTION:
Stream0273 2.0
END DESCRIPTION:
XS GIS Cut Line= 3
      1830374.97     13905124.97      1830325.00     13905075.00
      1830174.98     13905024.99
#Sta/Elev= 28
  4928.9 1988.41  4932.4 1988.41  4943.0 1986.58  4957.1 1982.42  4971.3 1978.75
  4985.4 1969.66  4994.0 1966.64  4994.3 1966.14  4997.8 1966.14  4998.0 1966.64
  4999.6 1966.64  5002.2 1966.64  5010.1 1968.17  5020.7 1971.24  5031.2 1975.97
  5041.7 1979.67  5052.3 1983.66  5062.8 1986.54  5073.4 1988.30  5083.9 1991.25
  5094.4 1994.65  5105.0 1996.81  5115.5 2000.50  5126.1 2001.90  5136.6 2002.63
  5147.1 2003.86  5155.0 2004.81  5157.7 2004.81
#Mann=3,-1,0
  4928.9     0.1       0  4994.0    0.05       0  4998.0     0.1       0
Bank Sta=4994,4998
Exp/Cntr=0.3,0.1

Type RM Length L Ch R = 1,459,252,252,252
BEGIN DESCRIPTION:
Stream0273 1.0
END DESCRIPTION:
XS GIS Cut Line= 3
      1830741.16     13904854.45      1830575.00     13904725.00
      1830188.52     13904712.92
#Sta/Elev= 30
  4789.7 2002.87  4800.4 2001.25  4843.8 1998.53  4858.3 1996.35  4886.2 1993.86
  4899.9 1990.73  4937.0 1985.62  4949.7 1982.12  4964.1 1973.17  4972.3 1965.81
  4978.6 1962.11  4986.8 1952.30  4991.1 1951.71  4991.3 1951.21  4994.8 1951.21
  4995.1 1951.71  4997.2 1954.15  5020.3 1954.12  5050.4 1965.84  5060.4 1970.86
  5070.4 1973.49  5110.4 1979.92  5157.9 1986.75  5162.9 1986.78  5210.4 1990.95
  5270.5 1994.09  5310.5 1994.74  5320.5 1995.82  5340.5 1995.54  5387.0 1996.23
#Mann=3,-1,0
  4789.7     0.1       0  4991.1    0.05       0  4995.1     0.1       0
Bank Sta=4991.1,4995.1
Exp/Cntr=0.3,0.1

Type RM Length L Ch R = 1,207,0,0,0
BEGIN DESCRIPTION:
Stream0273 0.0
END DESCRIPTION:
XS GIS Cut Line= 4
      1830815.45     13904747.08      1830688.75     13904523.21
      1830555.55     13904507.35      1830364.46     13904583.29
#Sta/Elev= 30
  4679.3 2001.08  4762.1 1996.29  4797.1 1993.68  4819.6 1990.44  4842.6 1989.19
  4877.9 1983.24  4888.1 1983.13  4909.7 1980.30  4931.4 1975.45  4935.3 1968.85
  4940.5 1968.85  4964.6 1954.03  4970.5 1948.47  4978.6 1947.99  4978.8 1947.49
  4982.6 1947.99  5010.8 1949.48  5047.2 1964.49  5052.2 1964.03  5068.4 1969.26
  5073.7 1969.26  5077.3 1971.15  5082.6 1971.02  5101.6 1975.31  5146.6 1976.76
  5178.9 1980.37  5185.2 1982.13  5200.4 1982.14  5244.6 1986.14  5276.3 1987.24
#Mann=4,-1,0
  4679.3   0.035       0  4940.5     0.1       0  4978.6    0.05       0
  4982.6     0.1       0
Bank Sta=4978.6,4982.6
Exp/Cntr=0.3,0.1

Chan Stop Cuts=-1