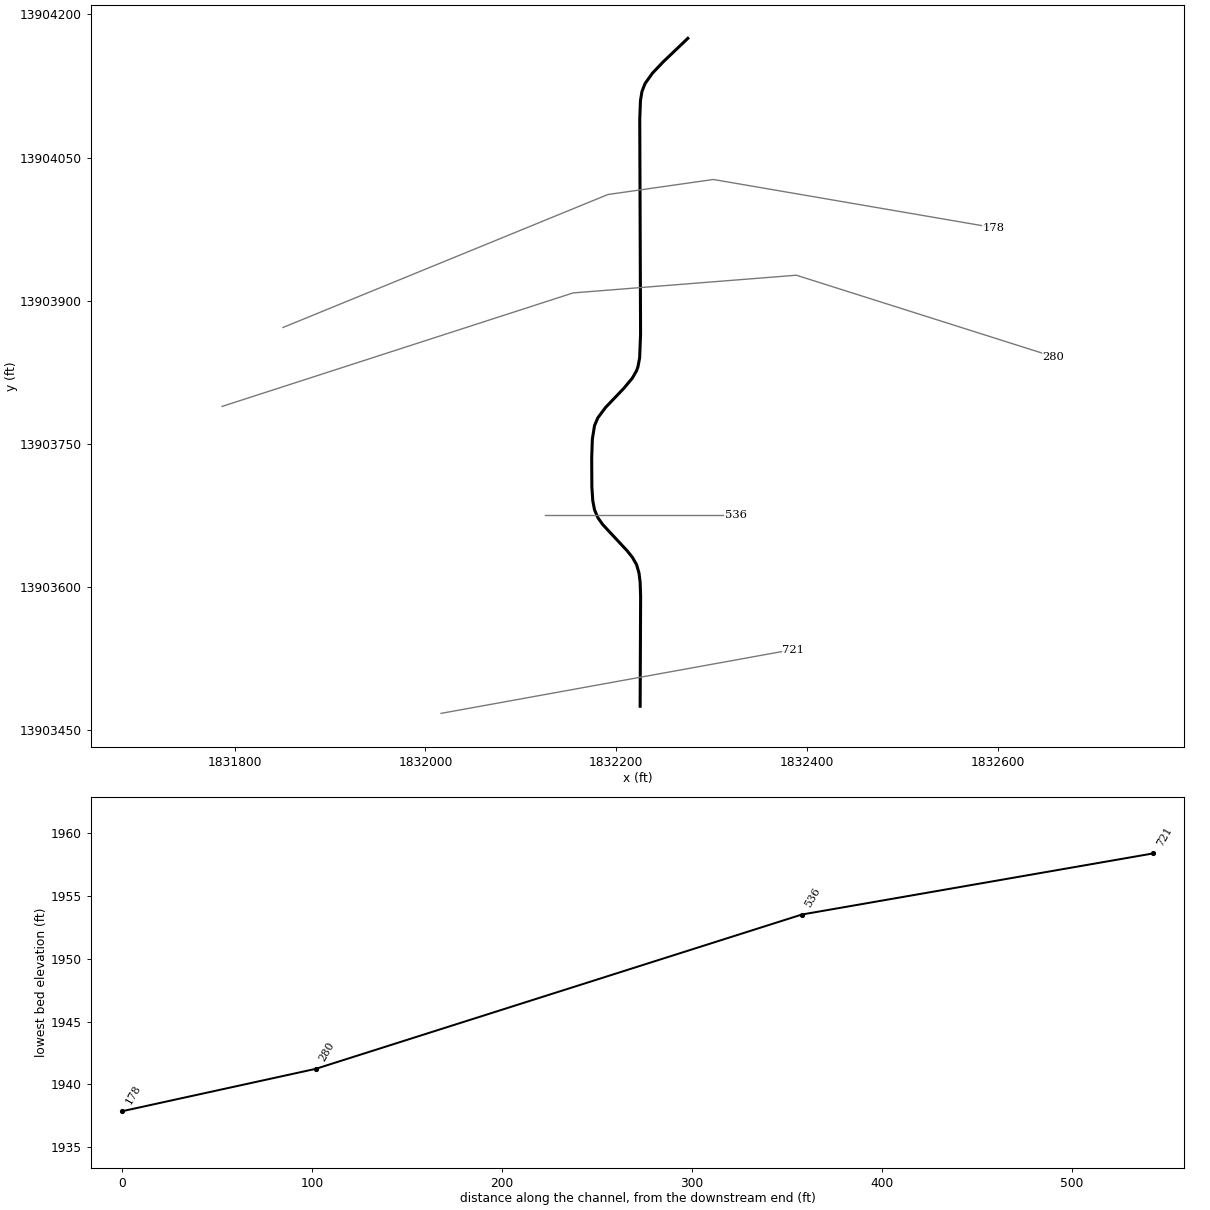
--- Stream0274.prj (project) ---

Proj Title=Stream0274 Base Level Engineering
Current Plan=p01
Default Exp/Contr=0.3,0.1
English Units
Geom File=g01
Flow File=f01
Plan File=p01
BEGIN DESCRIPTION:
Stream0274
END DESCRIPTION:

--- Stream0274.p01 (plan) ---

Plan Title=Multiple Run
Short Identifier=Multiple
Geom File=g01
Flow File=f01
Subcritical Flow
K Sum by GR= 0
Std Step Tol= 0.01
Critical Tol= 0.01
Num of Std Step Trials= 20
Max Error Tol= 0.3
Flow Tol Ratio= 0.001
Split Flow NTrial= 30
Split Flow Tol= 0.02
Split Flow Ratio= 0.02
Log Output Level= 0
Friction Slope Method= 1
Unsteady Friction Slope Method= 2
Unsteady Bridges Friction Slope Method= 1
Parabolic Critical Depth
Global Vel Dist=  1 , 1 , 1
Global Log Level= 0
CheckData=True
Encroach Param= -1, 0, 0, 0
BEGIN DESCRIPTION:
Multiple Run
END DESCRIPTION:

--- Stream0274.f01 (steady flow) ---

Flow Title=Multiple
Number of Profiles=7
Profile Names=10-year,25-year,50-year,1pct_min,100-year,1pct_plu,500-year
River Rch & RM= Stream0274,Reach-1,721
     514     848    1157     767    1531    3055    2641
Boundary for River Rch & Prof#=Stream0274,Reach-1,1
Up Type=0
Dn Type=3
Dn Slope=0.005
Boundary for River Rch & Prof#=Stream0274,Reach-1,2
Up Type=0
Dn Type=3
Dn Slope=0.005
Boundary for River Rch & Prof#=Stream0274,Reach-1,3
Up Type=0
Dn Type=3
Dn Slope=0.005
Boundary for River Rch & Prof#=Stream0274,Reach-1,4
Up Type=0
Dn Type=3
Dn Slope=0.005
Boundary for River Rch & Prof#=Stream0274,Reach-1,5
Up Type=0
Dn Type=3
Dn Slope=0.005
Boundary for River Rch & Prof#=Stream0274,Reach-1,6
Up Type=0
Dn Type=3
Dn Slope=0.005
Boundary for River Rch & Prof#=Stream0274,Reach-1,7
Up Type=0
Dn Type=3
Dn Slope=0.005

--- Stream0274.g01 (geometry) ---

Geom Title=Existing Conditions

River Reach=Stream0274,Reach-1
Reach XY= 30
      1832225.00     13903475.00      1832225.51     13903590.21
      1832224.99     13903605.00      1832223.83     13903614.52
      1832221.25     13903623.45      1832216.87     13903631.06
      1832211.20     13903638.15      1832185.81     13903665.37
      1832180.68     13903672.69      1832177.17     13903680.97
      1832175.38     13903690.27      1832174.40     13903704.95
      1832174.23     13903735.05      1832174.91     13903754.90
      1832177.17     13903769.02      1832180.68     13903777.31
      1832188.76     13903788.13      1832208.10     13903808.42
      1832216.85     13903818.94      1832221.22     13903826.56
      1832222.74     13903830.94      1832224.48     13903840.22
      1832225.45     13903864.81      1832224.59     13904090.17
      1832225.36     13904109.85      1832226.89     13904119.22
      1832230.14     13904127.59      1832237.92     13904138.51
      1832249.11     13904150.29      1832275.00     13904175.00

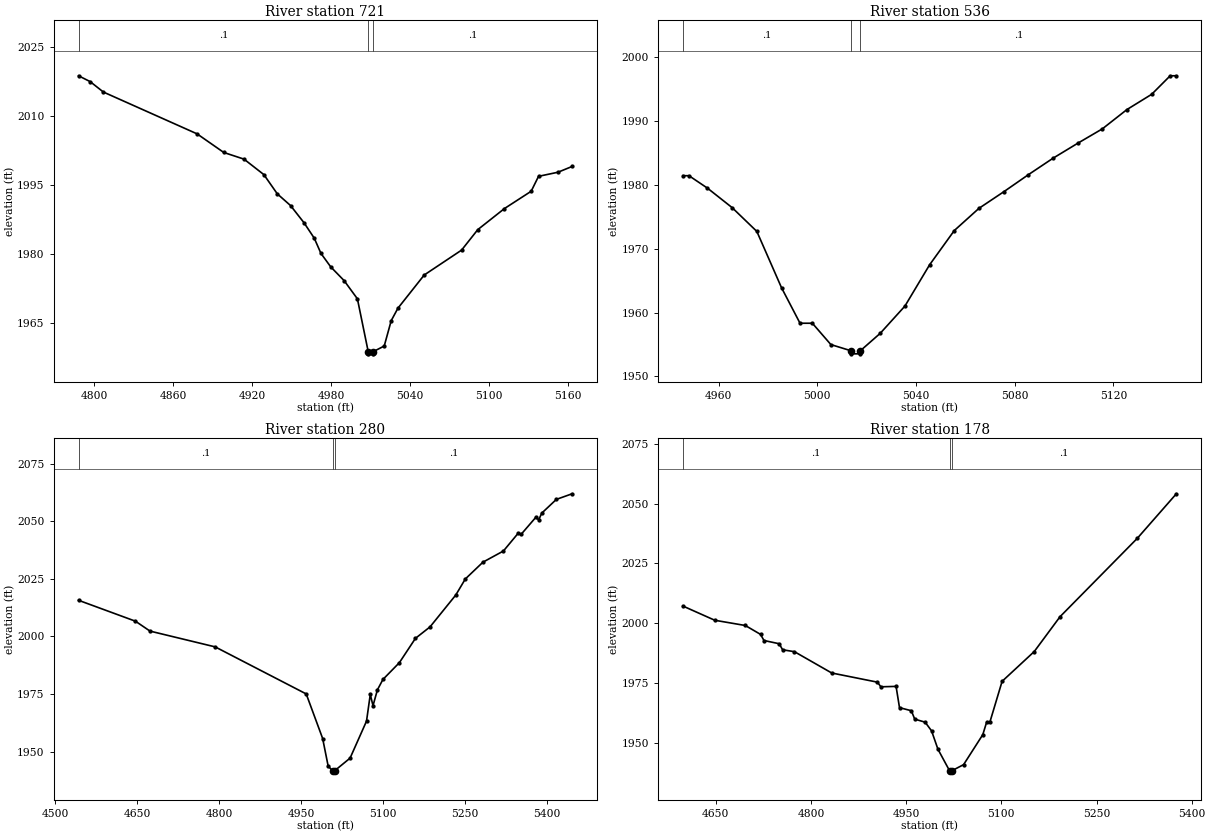
Type RM Length L Ch R = 1,721,185,185,185
BEGIN DESCRIPTION:
Stream0274 2.0
END DESCRIPTION:
XS GIS Cut Line= 2
      1832016.37     13903467.53      1832385.55     13903534.46
#Sta/Elev= 30
  4787.9 2018.75  4796.7 2017.49  4806.8 2015.22  4878.0 2006.15  4898.3 2002.11
  4913.7 2000.66  4928.8 1997.30  4939.0 1993.13  4949.1 1990.58  4959.3 1986.86
  4967.1 1983.51  4972.2 1980.20  4979.6 1977.29  4989.8 1974.30  4999.9 1970.35
  5008.1 1958.91  5008.3 1958.41  5011.8 1958.41  5012.1 1958.91  5020.3 1960.11
  5025.6 1965.61  5030.7 1968.31  5050.7 1975.52  5079.1 1980.92  5091.4 1985.36
  5111.7 1989.94  5132.0 1993.69  5137.6 1996.93  5152.4 1997.82  5163.1 1999.07
#Mann=3,-1,0
  4787.9     0.1       0  5008.1    0.05       0  5012.1     0.1       0
Bank Sta=5008.1,5012.1
Exp/Cntr=0.3,0.1

Type RM Length L Ch R = 1,536,256,256,256
BEGIN DESCRIPTION:
Stream0274 1.0
END DESCRIPTION:
XS GIS Cut Line= 3
      1832125.01     13903675.00      1832175.00     13903675.00
      1832325.01     13903675.00
#Sta/Elev= 27
  4945.5 1981.42  4948.0 1981.42  4955.5 1979.47  4965.5 1976.42  4975.5 1972.70
  4985.5 1963.89  4993.0 1958.33  4998.0 1958.33  5005.5 1954.99  5013.5 1954.04
  5013.7 1953.54  5017.2 1953.54  5017.5 1954.04  5025.5 1956.75  5035.5 1961.01
  5045.5 1967.47  5055.5 1972.83  5065.5 1976.31  5075.5 1978.89  5085.5 1981.57
  5095.5 1984.15  5105.5 1986.49  5115.5 1988.75  5125.5 1991.78  5135.5 1994.16
  5143.0 1997.06  5145.5 1997.06
#Mann=3,-1,0
  4945.5     0.1       0  5013.5    0.05       0  5017.5     0.1       0
Bank Sta=5013.5,5017.5
Exp/Cntr=0.3,0.1

Type RM Length L Ch R = 1,280,102,102,102
BEGIN DESCRIPTION:
Stream0274 0.0
END DESCRIPTION:
XS GIS Cut Line= 4
      1831786.91     13903789.25      1832154.75     13903908.19
      1832388.72     13903926.74      1832657.93     13903841.43
#Sta/Elev= 30
  4542.8 2015.72  4647.0 2006.64  4673.7 2002.34  4793.0 1995.49  4959.7 1975.06
  4989.8 1955.71  4999.9 1943.71  5007.9 1941.74  5008.1 1941.24  5011.9 1941.74
  5040.0 1947.19  5070.1 1963.25  5077.0 1974.84  5082.0 1969.96  5090.1 1976.86
  5100.2 1981.36  5130.3 1988.64  5159.7 1999.20  5186.4 2004.17  5233.6 2018.02
  5251.0 2024.97  5283.3 2032.27  5320.8 2037.12  5347.9 2044.86  5353.1 2044.32
  5380.1 2051.74  5385.4 2050.64  5391.0 2053.56  5417.7 2059.52  5446.5 2061.96
#Mann=3,-1,0
  4542.8     0.1       0  5007.9    0.05       0  5011.9     0.1       0
Bank Sta=5007.9,5011.9
Exp/Cntr=0.3,0.1

Type RM Length L Ch R = 1,178,0,0,0
BEGIN DESCRIPTION:
Stream0274 0.1
END DESCRIPTION:
XS GIS Cut Line= 4
      1831850.70     13903871.96      1832191.28     13904011.33
      1832301.73     13904027.07      1832595.67     13903976.58
#Sta/Elev= 30
  4598.0 2007.17  4648.4 2001.21  4696.5 1999.02  4720.5 1995.31  4725.9 1992.75
  4749.9 1991.40  4755.3 1988.87  4773.9 1988.08  4832.7 1979.17  4904.7 1975.34
  4910.1 1973.40  4934.1 1973.57  4939.5 1964.68  4958.1 1963.41  4963.5 1959.89
  4979.9 1958.61  4990.0 1955.00  5000.1 1947.29  5018.3 1938.36  5018.5 1937.86
  5022.3 1938.36  5040.5 1940.87  5070.8 1953.42  5076.7 1958.53  5081.8 1958.53
  5101.2 1975.69  5151.9 1988.15  5192.5 2002.70  5314.2 2035.44  5375.8 2054.07
#Mann=3,-1,0
  4598.0     0.1       0  5018.3    0.05       0  5022.3     0.1       0
Bank Sta=5018.3,5022.3
Exp/Cntr=0.3,0.1

Chan Stop Cuts=-1