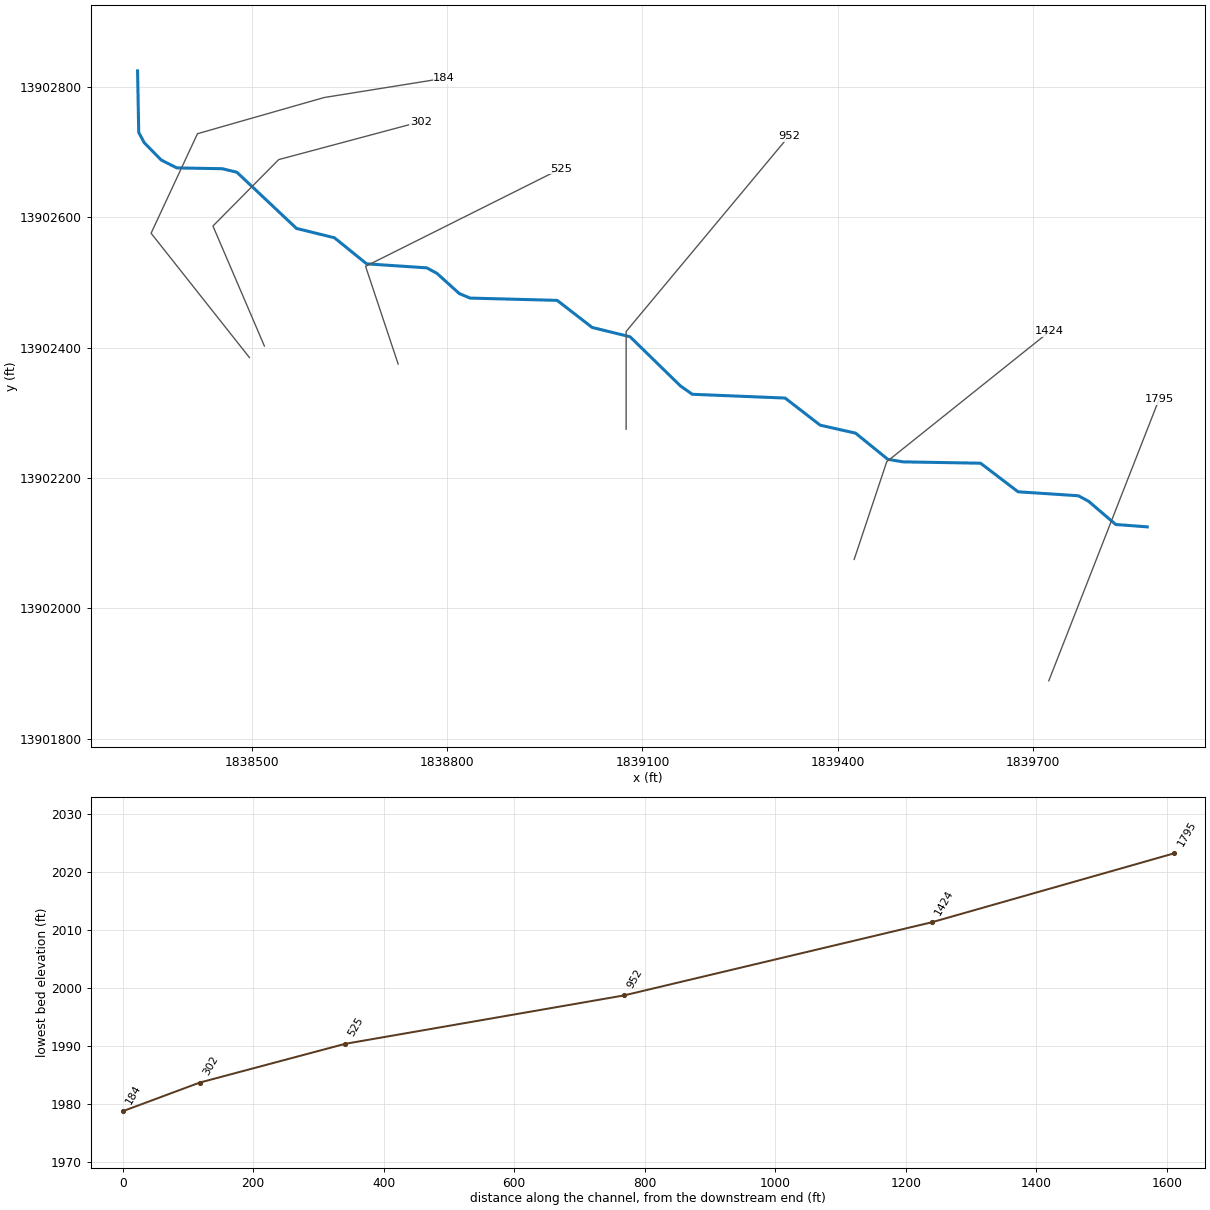
--- Stream0277.prj (project) ---

Proj Title=Stream0277 Base Level Engineering
Current Plan=p01
Default Exp/Contr=0.3,0.1
English Units
Geom File=g01
Flow File=f01
Plan File=p01
BEGIN DESCRIPTION:
Stream0277
END DESCRIPTION:

--- Stream0277.p01 (plan) ---

Plan Title=Multiple Run
Short Identifier=Multiple
Geom File=g01
Flow File=f01
Subcritical Flow
K Sum by GR= 0
Std Step Tol= 0.01
Critical Tol= 0.01
Num of Std Step Trials= 20
Max Error Tol= 0.3
Flow Tol Ratio= 0.001
Split Flow NTrial= 30
Split Flow Tol= 0.02
Split Flow Ratio= 0.02
Log Output Level= 0
Friction Slope Method= 1
Unsteady Friction Slope Method= 2
Unsteady Bridges Friction Slope Method= 1
Parabolic Critical Depth
Global Vel Dist=  1 , 1 , 1
Global Log Level= 0
CheckData=True
Encroach Param= -1, 0, 0, 0
BEGIN DESCRIPTION:
Multiple Run
END DESCRIPTION:

--- Stream0277.f01 (steady flow) ---

Flow Title=Multiple
Number of Profiles=7
Profile Names=10-year,25-year,50-year,1pct_min,100-year,1pct_plu,500-year
River Rch & RM= Stream0277,Reach-1,1795
     461     752    1019     671    1338    2669    2274
Boundary for River Rch & Prof#=Stream0277,Reach-1,1
Up Type=0
Dn Type=3
Dn Slope=0.005
Boundary for River Rch & Prof#=Stream0277,Reach-1,2
Up Type=0
Dn Type=3
Dn Slope=0.005
Boundary for River Rch & Prof#=Stream0277,Reach-1,3
Up Type=0
Dn Type=3
Dn Slope=0.005
Boundary for River Rch & Prof#=Stream0277,Reach-1,4
Up Type=0
Dn Type=3
Dn Slope=0.005
Boundary for River Rch & Prof#=Stream0277,Reach-1,5
Up Type=0
Dn Type=3
Dn Slope=0.005
Boundary for River Rch & Prof#=Stream0277,Reach-1,6
Up Type=0
Dn Type=3
Dn Slope=0.005
Boundary for River Rch & Prof#=Stream0277,Reach-1,7
Up Type=0
Dn Type=3
Dn Slope=0.005

--- Stream0277.g01 (geometry) ---

Geom Title=Existing Conditions

River Reach=Stream0277,Reach-1
Reach XY= 30
      1839875.00     13902125.00      1839826.51     13902128.64
      1839784.75     13902164.39      1839769.08     13902172.77
      1839676.60     13902178.85      1839619.06     13902222.73
      1839499.92     13902224.81      1839476.56     13902228.76
      1839427.18     13902268.88      1839372.82     13902281.12
      1839319.07     13902322.75      1839176.47     13902328.55
      1839158.25     13902341.46      1839081.05     13902416.84
      1839022.83     13902431.14      1838969.07     13902472.75
      1838835.51     13902476.23      1838818.94     13902483.14
      1838784.63     13902514.11      1838769.02     13902522.64
      1838676.58     13902528.83      1838627.17     13902568.86
      1838568.95     13902583.16      1838477.42     13902669.46
      1838454.94     13902674.86      1838385.32     13902676.09
      1838361.28     13902688.20      1838335.26     13902714.76
      1838326.76     13902730.53      1838325.00     13902825.00

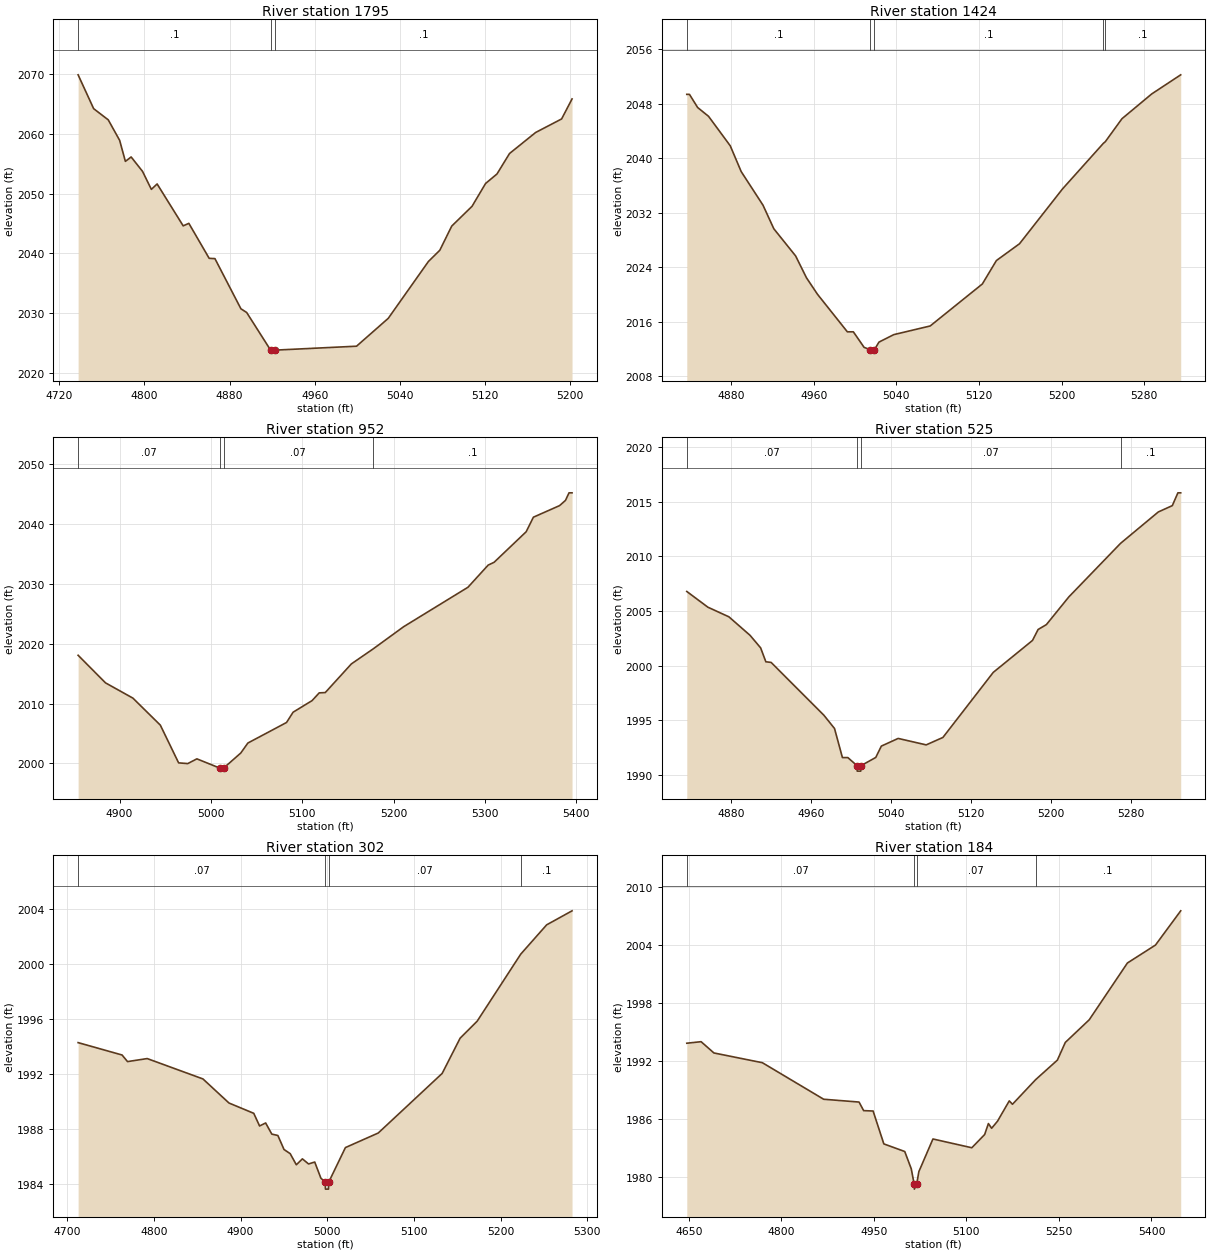
Type RM Length L Ch R = 1,1795,371,371,371
BEGIN DESCRIPTION:
Stream0277 4.0
END DESCRIPTION:
XS GIS Cut Line= 2
      1839723.80     13901888.68      1839892.97     13902320.64
#Sta/Elev= 30
  4737.7 2069.88  4752.3 2064.21  4766.0 2062.34  4776.7 2058.91  4782.1 2055.38
  4787.5 2056.12  4798.2 2053.71  4806.5 2050.69  4811.9 2051.60  4836.4 2044.58
  4841.7 2045.00  4860.8 2039.14  4866.2 2039.09  4890.6 2030.69  4896.0 2030.07
  4918.5 2023.76  4918.7 2023.26  4922.5 2023.76  4999.2 2024.42  5029.0 2029.09
  5066.7 2038.61  5077.4 2040.49  5088.6 2044.54  5107.7 2047.86  5120.4 2051.68
  5131.1 2053.27  5142.9 2056.70  5167.4 2060.22  5191.8 2062.49  5201.6 2065.84
#Mann=3,-1,0
  4737.7     0.1       0  4918.5    0.05       0  4922.5     0.1       0
Bank Sta=4918.5,4922.5
Exp/Cntr=0.3,0.1

Type RM Length L Ch R = 1,1424,472,472,472
BEGIN DESCRIPTION:
Stream0277 3.0
END DESCRIPTION:
XS GIS Cut Line= 3
      1839425.01     13902075.02      1839475.00     13902225.00
      1839725.04     13902425.03
#Sta/Elev= 30
  4837.1 2049.38  4839.7 2049.38  4847.6 2047.45  4858.2 2046.15  4879.2 2041.82
  4889.8 2038.03  4910.9 2033.10  4921.4 2029.63  4942.5 2025.64  4953.0 2022.43
  4963.6 2020.02  4992.6 2014.49  4998.4 2014.49  5008.8 2012.21  5014.8 2011.86
  5015.1 2011.36  5018.6 2011.36  5018.8 2011.86  5023.2 2012.98  5037.6 2014.08
  5072.8 2015.35  5123.3 2021.52  5136.9 2024.96  5159.3 2027.43  5200.9 2035.48
  5240.6 2042.20  5242.3 2042.41  5258.5 2045.80  5287.3 2049.44  5315.4 2052.25
#Mann=5,-1,0
  4837.1     0.1       0  5014.8    0.05       0  5018.8     0.1       0
  5240.6    0.07       0  5242.3     0.1       0
Bank Sta=5014.8,5018.8
Exp/Cntr=0.3,0.1

Type RM Length L Ch R = 1,952,427,427,427
BEGIN DESCRIPTION:
Stream0277 2.0
END DESCRIPTION:
XS GIS Cut Line= 3
      1839075.00     13902274.96      1839075.00     13902425.00
      1839325.03     13902725.03
#Sta/Elev= 30
  4854.7 2018.06  4884.7 2013.45  4914.7 2010.90  4944.7 2006.39  4964.7 2000.09
  4974.7 1999.97  4984.7 2000.76  5009.9 1999.21  5010.2 1998.71  5013.7 1998.71
  5013.9 1999.21  5032.7 2001.73  5040.5 2003.40  5082.8 2006.83  5090.0 2008.55
  5110.8 2010.49  5118.6 2011.78  5125.2 2011.83  5153.8 2016.62  5177.5 2019.11
  5211.1 2022.84  5281.4 2029.42  5303.5 2033.12  5310.0 2033.59  5345.1 2038.69
  5353.0 2041.12  5381.6 2043.05  5388.1 2043.92  5392.0 2045.19  5395.3 2045.19
#Mann=4,-1,0
  4854.7    0.07       0  5009.9    0.05       0  5013.9    0.07       0
  5177.5     0.1       0
Bank Sta=5009.9,5013.9
Exp/Cntr=0.3,0.1

Type RM Length L Ch R = 1,525,223,223,223
BEGIN DESCRIPTION:
Stream0277 1.0
END DESCRIPTION:
XS GIS Cut Line= 3
      1838724.99     13902375.02      1838675.00     13902525.00
      1838974.99     13902675.00
#Sta/Elev= 30
  4836.1 2006.78  4857.2 2005.34  4878.2 2004.46  4899.3 2002.77  4909.9 2001.62
  4915.1 2000.35  4920.4 2000.29  4973.1 1995.46  4983.7 1994.25  4991.6 1991.59
  4997.0 1991.59  5006.2 1990.85  5006.4 1990.35  5009.9 1990.35  5010.2 1990.85
  5024.9 1991.60  5030.5 1992.64  5047.3 1993.34  5075.3 1992.75  5092.0 1993.43
  5142.3 1999.38  5181.5 2002.30  5187.1 2003.30  5195.4 2003.75  5217.8 2006.28
  5269.5 2011.18  5307.2 2014.05  5321.2 2014.63  5326.8 2015.80  5329.6 2015.80
#Mann=4,-1,0
  4836.1    0.07       0  5006.2    0.05       0  5010.2    0.07       0
  5269.5     0.1       0
Bank Sta=5006.2,5010.2
Exp/Cntr=0.3,0.1

Type RM Length L Ch R = 1,302,118,118,118
BEGIN DESCRIPTION:
Stream0277 0.0
END DESCRIPTION:
XS GIS Cut Line= 4
      1838519.67     13902402.64      1838440.70     13902586.88
      1838541.60     13902688.82      1838759.75     13902747.16
#Sta/Elev= 30
  4712.6 1994.30  4763.3 1993.40  4769.6 1992.92  4792.3 1993.14  4856.6 1991.66
  4886.6 1989.91  4915.2 1989.16  4921.9 1988.24  4928.9 1988.46  4936.0 1987.65
  4943.0 1987.55  4950.1 1986.53  4957.2 1986.23  4964.3 1985.42  4971.3 1985.85
  4978.4 1985.48  4985.5 1985.62  4992.6 1984.45  4997.6 1984.15  4997.9 1983.65
  5001.4 1983.65  5001.6 1984.15  5020.9 1986.67  5058.8 1987.73  5132.5 1992.06
  5153.2 1994.62  5172.9 1995.86  5223.1 2000.73  5253.0 2002.86  5282.3 2003.88
#Mann=4,-1,0
  4712.6    0.07       0  4997.6    0.05       0  5001.6    0.07       0
  5223.1     0.1       0
Bank Sta=4997.6,5001.6
Exp/Cntr=0.3,0.1

Type RM Length L Ch R = 1,184,0,0,0
BEGIN DESCRIPTION:
Stream0277 T
END DESCRIPTION:
XS GIS Cut Line= 5
      1838496.77     13902384.88      1838345.76     13902575.81
      1838416.94     13902728.59      1838611.38     13902784.14
      1838795.43     13902813.66
#Sta/Elev= 30
  4646.8 1993.83  4670.0 1993.99  4690.8 1992.82  4769.3 1991.81  4868.7 1988.02
  4926.0 1987.73  4933.5 1986.84  4948.8 1986.80  4966.2 1983.39  5000.1 1982.60
  5010.7 1980.80  5015.4 1979.20  5015.7 1978.70  5019.4 1979.20  5023.0 1980.52
  5045.8 1983.90  5108.8 1982.99  5129.6 1984.36  5135.7 1985.50  5140.9 1985.01
  5150.4 1985.74  5169.5 1987.85  5174.7 1987.50  5212.2 1990.05  5247.5 1992.08
  5260.3 1993.91  5299.1 1996.26  5361.0 2002.15  5406.5 2004.01  5447.4 2007.56
#Mann=4,-1,0
  4646.8    0.07       0  5015.4    0.05       0  5019.4    0.07       0
  5212.2     0.1       0
Bank Sta=5015.4,5019.4
Exp/Cntr=0.3,0.1

Chan Stop Cuts=-1