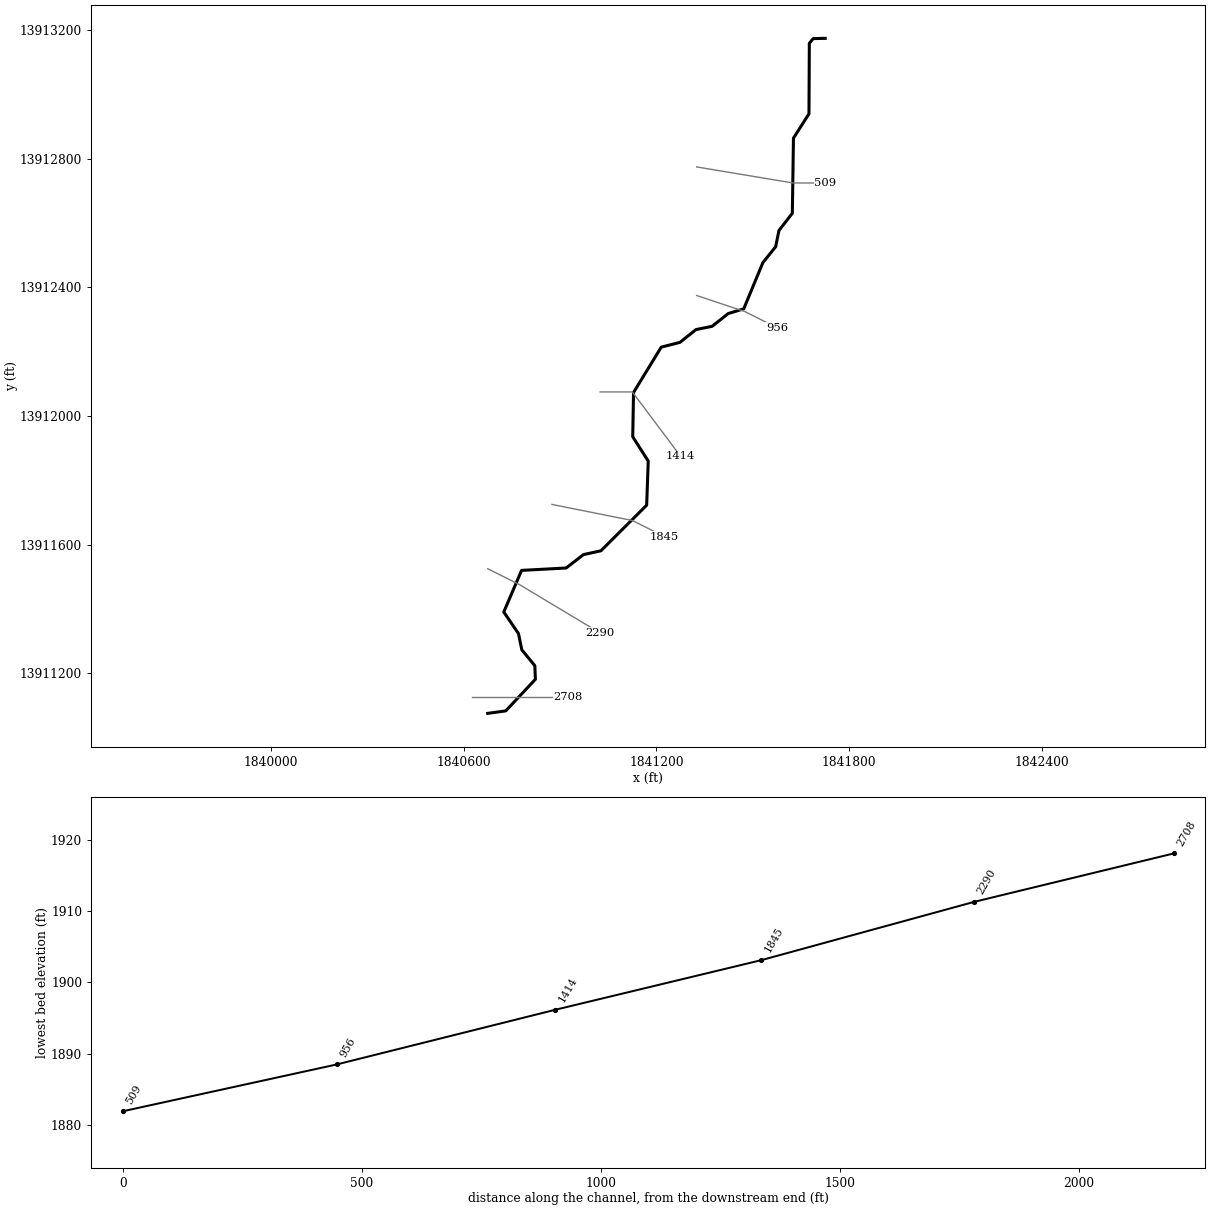
--- Stream0283.prj (project) ---

Proj Title=Stream0283 Base Level Engineering
Current Plan=p01
Default Exp/Contr=0.3,0.1
English Units
Geom File=g01
Flow File=f01
Plan File=p01
BEGIN DESCRIPTION:
Stream0283
END DESCRIPTION:

--- Stream0283.p01 (plan) ---

Plan Title=Multiple Run
Short Identifier=Multiple
Geom File=g01
Flow File=f01
Subcritical Flow
K Sum by GR= 0
Std Step Tol= 0.01
Critical Tol= 0.01
Num of Std Step Trials= 20
Max Error Tol= 0.3
Flow Tol Ratio= 0.001
Split Flow NTrial= 30
Split Flow Tol= 0.02
Split Flow Ratio= 0.02
Log Output Level= 0
Friction Slope Method= 1
Unsteady Friction Slope Method= 2
Unsteady Bridges Friction Slope Method= 1
Parabolic Critical Depth
Global Vel Dist=  1 , 1 , 1
Global Log Level= 0
CheckData=True
Encroach Param= -1, 0, 0, 0
BEGIN DESCRIPTION:
Multiple Run
END DESCRIPTION:

--- Stream0283.f01 (steady flow) ---

Flow Title=Multiple
Number of Profiles=7
Profile Names=10-year,25-year,50-year,1pct_min,100-year,1pct_plu,500-year
River Rch & RM= Stream0283,Reach-1,2708
    1053    1808    2532    1715    3422    6829    6179
Boundary for River Rch & Prof#=Stream0283,Reach-1,1
Up Type=0
Dn Type=3
Dn Slope=0.005
Boundary for River Rch & Prof#=Stream0283,Reach-1,2
Up Type=0
Dn Type=3
Dn Slope=0.005
Boundary for River Rch & Prof#=Stream0283,Reach-1,3
Up Type=0
Dn Type=3
Dn Slope=0.005
Boundary for River Rch & Prof#=Stream0283,Reach-1,4
Up Type=0
Dn Type=3
Dn Slope=0.005
Boundary for River Rch & Prof#=Stream0283,Reach-1,5
Up Type=0
Dn Type=3
Dn Slope=0.005
Boundary for River Rch & Prof#=Stream0283,Reach-1,6
Up Type=0
Dn Type=3
Dn Slope=0.005
Boundary for River Rch & Prof#=Stream0283,Reach-1,7
Up Type=0
Dn Type=3
Dn Slope=0.005

--- Stream0283.g01 (geometry) ---

Geom Title=Existing Conditions

River Reach=Stream0283,Reach-1
Reach XY= 30
      1840675.00     13911075.00      1840731.24     13911082.75
      1840823.40     13911181.03      1840821.69     13911223.26
      1840781.15     13911272.80      1840770.78     13911323.28
      1840725.07     13911390.40      1840780.41     13911519.82
      1840919.06     13911527.25      1840972.83     13911568.86
      1841027.30     13911580.83      1841169.55     13911722.55
      1841174.49     13911859.78      1841126.21     13911935.51
      1841128.74     13912073.44      1841215.00     13912214.37
      1841273.24     13912229.20      1841322.81     13912268.92
      1841373.31     13912279.15      1841423.15     13912318.76
      1841471.50     13912333.46      1841531.08     13912477.19
      1841570.84     13912526.72      1841581.12     13912577.18
      1841622.76     13912630.93      1841626.22     13912864.50
      1841674.48     13912940.22      1841675.61     13913159.39
      1841687.43     13913174.17      1841725.00     13913175.00

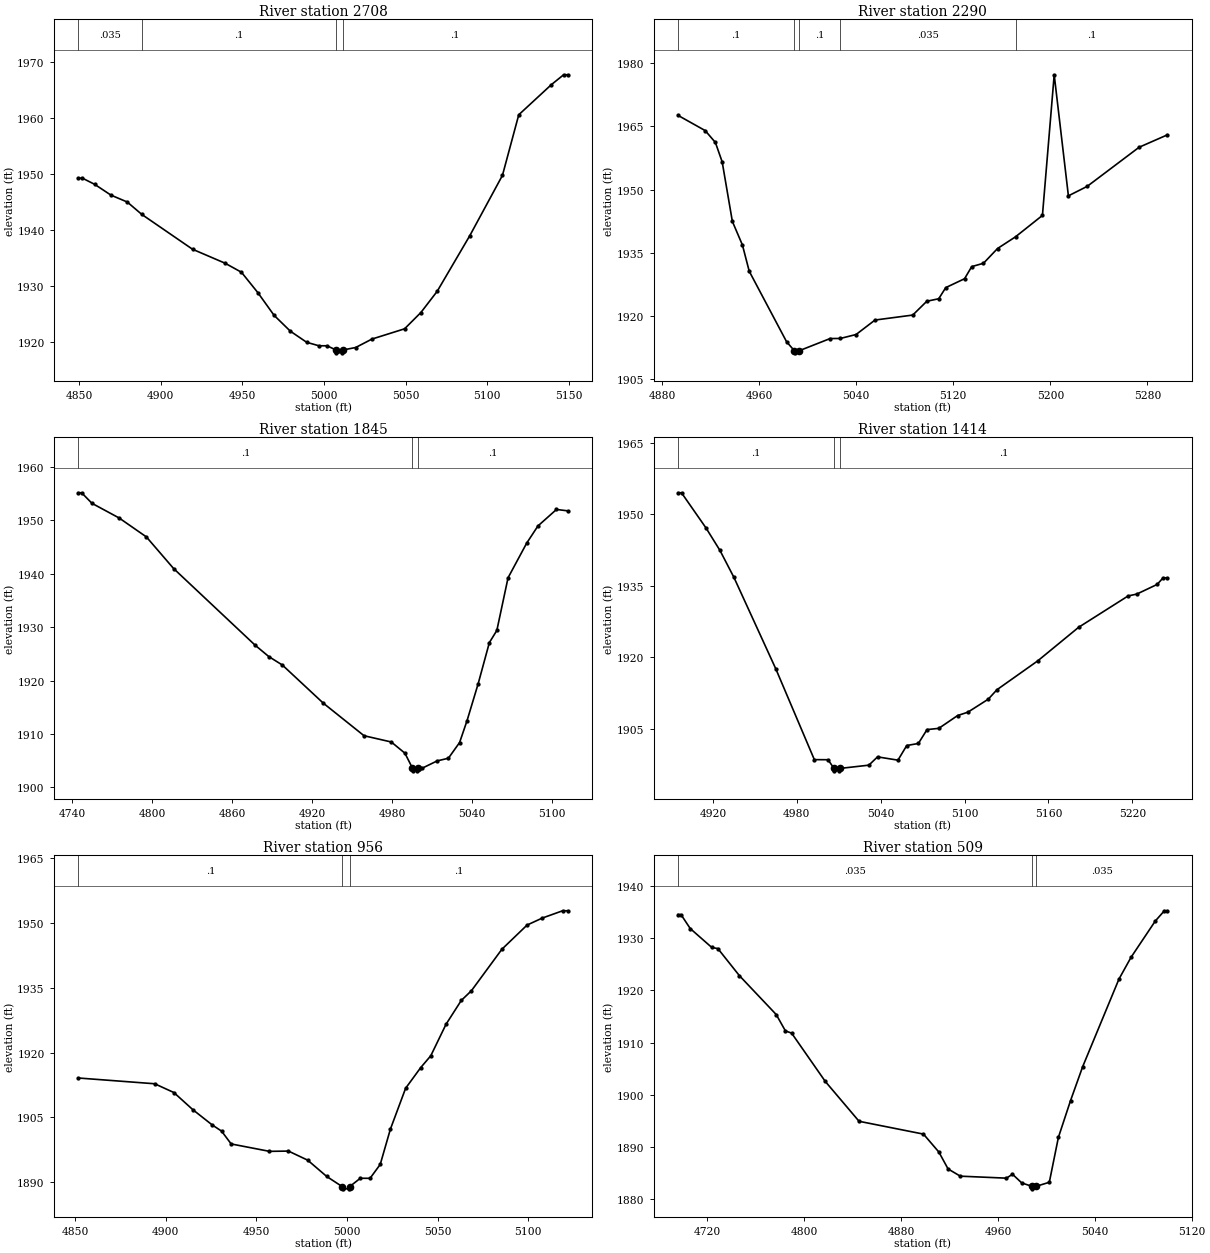
Type RM Length L Ch R = 1,2708,418,418,418
BEGIN DESCRIPTION:
Stream0283 6.0
END DESCRIPTION:
XS GIS Cut Line= 3
      1840625.03     13911125.00      1840775.00     13911125.00
      1840925.03     13911125.00
#Sta/Elev= 30
  4849.4 1949.25  4851.9 1949.25  4859.4 1948.15  4869.4 1946.22  4879.4 1944.99
  4888.3 1942.78  4919.4 1936.56  4939.4 1934.06  4949.4 1932.45  4959.4 1928.83
  4969.4 1924.76  4979.4 1921.92  4989.4 1919.94  4996.9 1919.32  5001.9 1919.32
  5007.4 1918.56  5007.6 1918.06  5011.1 1918.06  5011.4 1918.56  5019.4 1919.01
  5029.4 1920.52  5049.4 1922.35  5059.4 1925.26  5069.4 1929.05  5089.4 1938.99
  5109.4 1949.75  5119.4 1960.57  5139.4 1965.95  5146.9 1967.71  5149.4 1967.71
#Mann=4,-1,0
  4849.4   0.035       0  4888.3     0.1       0  5007.4    0.05       0
  5011.4     0.1       0
Bank Sta=5007.4,5011.4
Exp/Cntr=0.3,0.1

Type RM Length L Ch R = 1,2290,445,445,445
BEGIN DESCRIPTION:
Stream0283 5.0
END DESCRIPTION:
XS GIS Cut Line= 3
      1840674.96     13911525.02      1840775.00     13911475.00
      1841025.01     13911325.00
#Sta/Elev= 30
  4893.1 1967.60  4915.5 1963.99  4923.9 1961.18  4929.5 1956.58  4937.9 1942.45
  4946.2 1936.85  4951.8 1930.63  4982.6 1913.90  4989.0 1911.77  4989.2 1911.27
  4993.0 1911.77  5018.5 1914.66  5026.9 1914.68  5039.9 1915.62  5055.5 1919.05
  5086.6 1920.23  5098.2 1923.51  5108.0 1924.10  5113.8 1926.74  5129.3 1928.85
  5135.2 1931.72  5144.9 1932.52  5156.5 1936.02  5171.3 1938.79  5193.5 1943.87
  5203.2 1977.23  5214.9 1948.51  5230.4 1950.76  5273.2 1960.04  5296.5 1962.98
#Mann=5,-1,0
  4893.1     0.1       0  4989.0    0.05       0  4993.0     0.1       0
  5026.9   0.035       0  5171.3     0.1       0
Bank Sta=4989,4993
Exp/Cntr=0.3,0.1

Type RM Length L Ch R = 1,1845,431,431,431
BEGIN DESCRIPTION:
Stream0283 4.0
END DESCRIPTION:
XS GIS Cut Line= 3
      1840875.03     13911724.99      1841125.00     13911675.00
      1841224.98     13911625.01
#Sta/Elev= 30
  4744.8 1955.15  4747.3 1955.15  4755.0 1953.18  4775.4 1950.43  4795.8 1946.89
  4816.2 1940.97  4877.3 1926.62  4887.5 1924.50  4897.7 1922.91  4928.3 1915.79
  4958.9 1909.68  4979.3 1908.51  4989.5 1906.42  4995.2 1903.61  4995.4 1903.11
  4998.9 1903.11  4999.2 1903.61  5002.5 1903.61  5013.7 1904.97  5022.1 1905.47
  5030.5 1908.41  5036.1 1912.52  5044.4 1919.40  5052.8 1927.11  5058.4 1929.38
  5066.8 1939.24  5080.8 1945.74  5089.2 1948.94  5103.1 1952.03  5111.5 1951.77
#Mann=3,-1,0
  4744.8     0.1       0  4995.2    0.05       0  4999.2     0.1       0
Bank Sta=4995.2,4999.2
Exp/Cntr=0.3,0.1

Type RM Length L Ch R = 1,1414,458,458,458
BEGIN DESCRIPTION:
Stream0283 3.0
END DESCRIPTION:
XS GIS Cut Line= 3
      1841024.98     13912075.00      1841125.00     13912075.00
      1841274.99     13911875.02
#Sta/Elev= 30
  4895.1 1954.48  4897.6 1954.48  4915.1 1947.11  4925.1 1942.39  4935.1 1936.73
  4965.1 1917.51  4992.6 1898.51  5002.4 1898.49  5006.7 1896.66  5006.9 1896.16
  5010.4 1896.16  5010.7 1896.66  5031.6 1897.35  5037.8 1899.09  5052.4 1898.40
  5058.7 1901.47  5067.0 1901.90  5073.2 1904.81  5081.6 1905.07  5095.1 1907.76
  5102.4 1908.46  5117.0 1911.19  5123.2 1913.17  5152.4 1919.23  5181.6 1926.26
  5217.0 1932.84  5223.2 1933.23  5237.8 1935.26  5242.0 1936.63  5245.1 1936.63
#Mann=3,-1,0
  4895.1     0.1       0  5006.7    0.05       0  5010.7     0.1       0
Bank Sta=5006.7,5010.7
Exp/Cntr=0.3,0.1

Type RM Length L Ch R = 1,956,447,447,447
BEGIN DESCRIPTION:
Stream0283 2.0
END DESCRIPTION:
XS GIS Cut Line= 3
      1841325.02     13912374.99      1841475.00     13912325.00
      1841575.00     13912275.00
#Sta/Elev= 30
  4851.8 1914.12  4893.9 1912.79  4904.5 1910.76  4915.0 1906.78  4925.6 1903.28
  4930.8 1901.84  4936.1 1898.87  4957.2 1897.16  4967.7 1897.22  4978.3 1895.12
  4988.8 1891.35  4997.4 1888.99  4997.6 1888.49  5001.1 1888.49  5001.4 1888.99
  5007.3 1890.93  5012.7 1890.93  5018.3 1894.13  5023.9 1902.28  5032.3 1911.74
  5040.6 1916.51  5046.2 1919.27  5054.6 1926.55  5063.0 1932.05  5068.6 1934.30
  5085.4 1943.89  5099.3 1949.49  5107.7 1951.11  5118.9 1952.79  5121.7 1952.79
#Mann=3,-1,0
  4851.8     0.1       0  4997.4    0.05       0  5001.4     0.1       0
Bank Sta=4997.4,5001.4
Exp/Cntr=0.3,0.1

Type RM Length L Ch R = 1,509,0,0,0
BEGIN DESCRIPTION:
Stream0283 1.0
END DESCRIPTION:
XS GIS Cut Line= 3
      1841325.02     13912775.00      1841625.00     13912725.00
      1841724.99     13912725.00
#Sta/Elev= 30
  4695.8 1934.55  4698.3 1934.55  4705.9 1931.88  4723.7 1928.25  4728.7 1928.04
  4746.5 1922.84  4776.9 1915.38  4784.5 1912.24  4789.6 1911.82  4817.4 1902.55
  4845.3 1894.90  4898.5 1892.44  4911.2 1889.00  4918.8 1885.76  4928.9 1884.37
  4967.0 1883.99  4972.0 1884.74  4979.6 1883.08  4987.8 1882.44  4988.0 1881.94
  4991.8 1882.44  5002.4 1883.20  5009.9 1891.81  5019.9 1898.85  5029.9 1905.35
  5059.9 1922.18  5069.9 1926.37  5089.9 1933.32  5097.4 1935.29  5099.9 1935.29
#Mann=3,-1,0
  4695.8   0.035       0  4987.8   0.035       0  4991.8   0.035       0
Bank Sta=4987.8,4991.8
Exp/Cntr=0.3,0.1

Chan Stop Cuts=-1