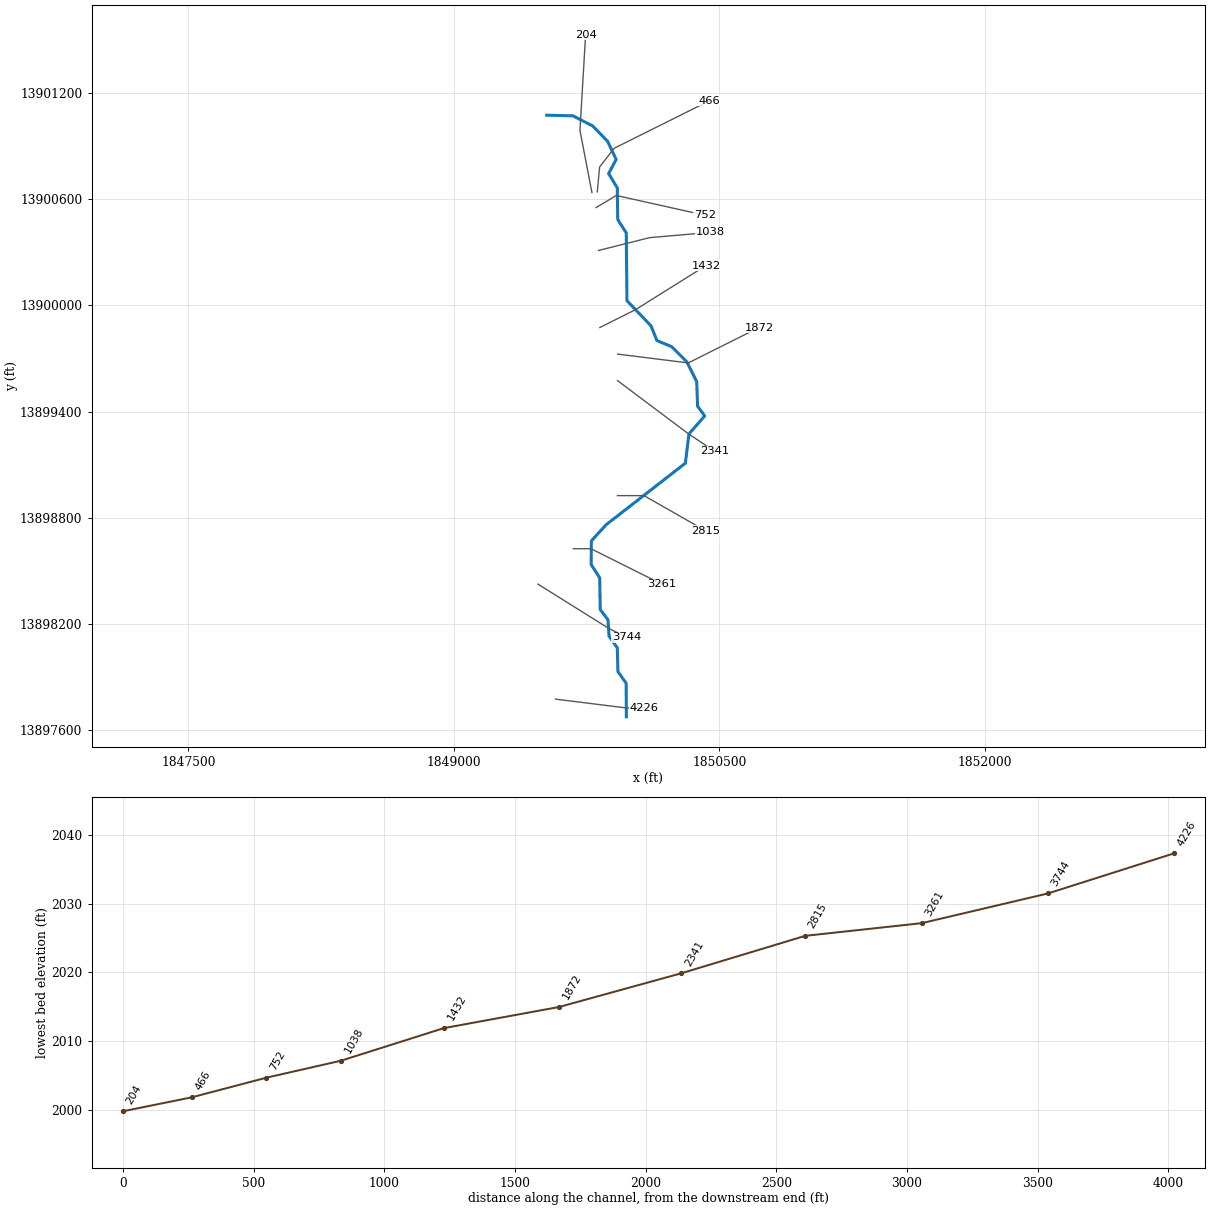
--- Stream0284.prj (project) ---

Proj Title=Stream0284 Base Level Engineering
Current Plan=p01
Default Exp/Contr=0.3,0.1
English Units
Geom File=g01
Flow File=f01
Plan File=p01
BEGIN DESCRIPTION:
Stream0284
END DESCRIPTION:

--- Stream0284.p01 (plan) ---

Plan Title=Multiple Run
Short Identifier=Multiple
Geom File=g01
Flow File=f01
Subcritical Flow
K Sum by GR= 0
Std Step Tol= 0.01
Critical Tol= 0.01
Num of Std Step Trials= 20
Max Error Tol= 0.3
Flow Tol Ratio= 0.001
Split Flow NTrial= 30
Split Flow Tol= 0.02
Split Flow Ratio= 0.02
Log Output Level= 0
Friction Slope Method= 1
Unsteady Friction Slope Method= 2
Unsteady Bridges Friction Slope Method= 1
Parabolic Critical Depth
Global Vel Dist=  1 , 1 , 1
Global Log Level= 0
CheckData=True
Encroach Param= -1, 0, 0, 0
BEGIN DESCRIPTION:
Multiple Run
END DESCRIPTION:

--- Stream0284.f01 (steady flow) ---

Flow Title=Multiple
Number of Profiles=7
Profile Names=10-year,25-year,50-year,1pct_min,100-year,1pct_plu,500-year
River Rch & RM= Stream0284,Reach-1,4226
    1843    3237    4601    3155    6294   12559   11653
Boundary for River Rch & Prof#=Stream0284,Reach-1,1
Up Type=0
Dn Type=3
Dn Slope=0.005
Boundary for River Rch & Prof#=Stream0284,Reach-1,2
Up Type=0
Dn Type=3
Dn Slope=0.005
Boundary for River Rch & Prof#=Stream0284,Reach-1,3
Up Type=0
Dn Type=3
Dn Slope=0.005
Boundary for River Rch & Prof#=Stream0284,Reach-1,4
Up Type=0
Dn Type=3
Dn Slope=0.005
Boundary for River Rch & Prof#=Stream0284,Reach-1,5
Up Type=0
Dn Type=3
Dn Slope=0.005
Boundary for River Rch & Prof#=Stream0284,Reach-1,6
Up Type=0
Dn Type=3
Dn Slope=0.005
Boundary for River Rch & Prof#=Stream0284,Reach-1,7
Up Type=0
Dn Type=3
Dn Slope=0.005

--- Stream0284.g01 (geometry) ---

Geom Title=Existing Conditions

River Reach=Stream0284,Reach-1
Reach XY= 30
      1849975.00     13897675.00      1849973.79     13897864.50
      1849927.27     13897930.94      1849923.77     13898064.49
      1849877.36     13898130.98      1849871.14     13898223.40
      1849827.26     13898280.94      1849824.48     13898459.78
      1849776.21     13898535.51      1849777.04     13898669.15
      1849861.76     13898761.38      1850308.57     13899108.23
      1850328.57     13899273.53      1850417.67     13899374.90
      1850377.48     13899430.86      1850372.75     13899569.07
      1850316.87     13899681.07      1850231.05     13899766.84
      1850147.86     13899801.16      1850114.21     13899884.66
      1849978.54     13900026.46      1849974.48     13900409.78
      1849926.22     13900485.51      1849923.76     13900664.50
      1849874.79     13900745.21      1849917.44     13900825.00
      1849869.20     13900927.30      1849784.71     13901014.25
      1849673.46     13901071.28      1849525.00     13901075.00

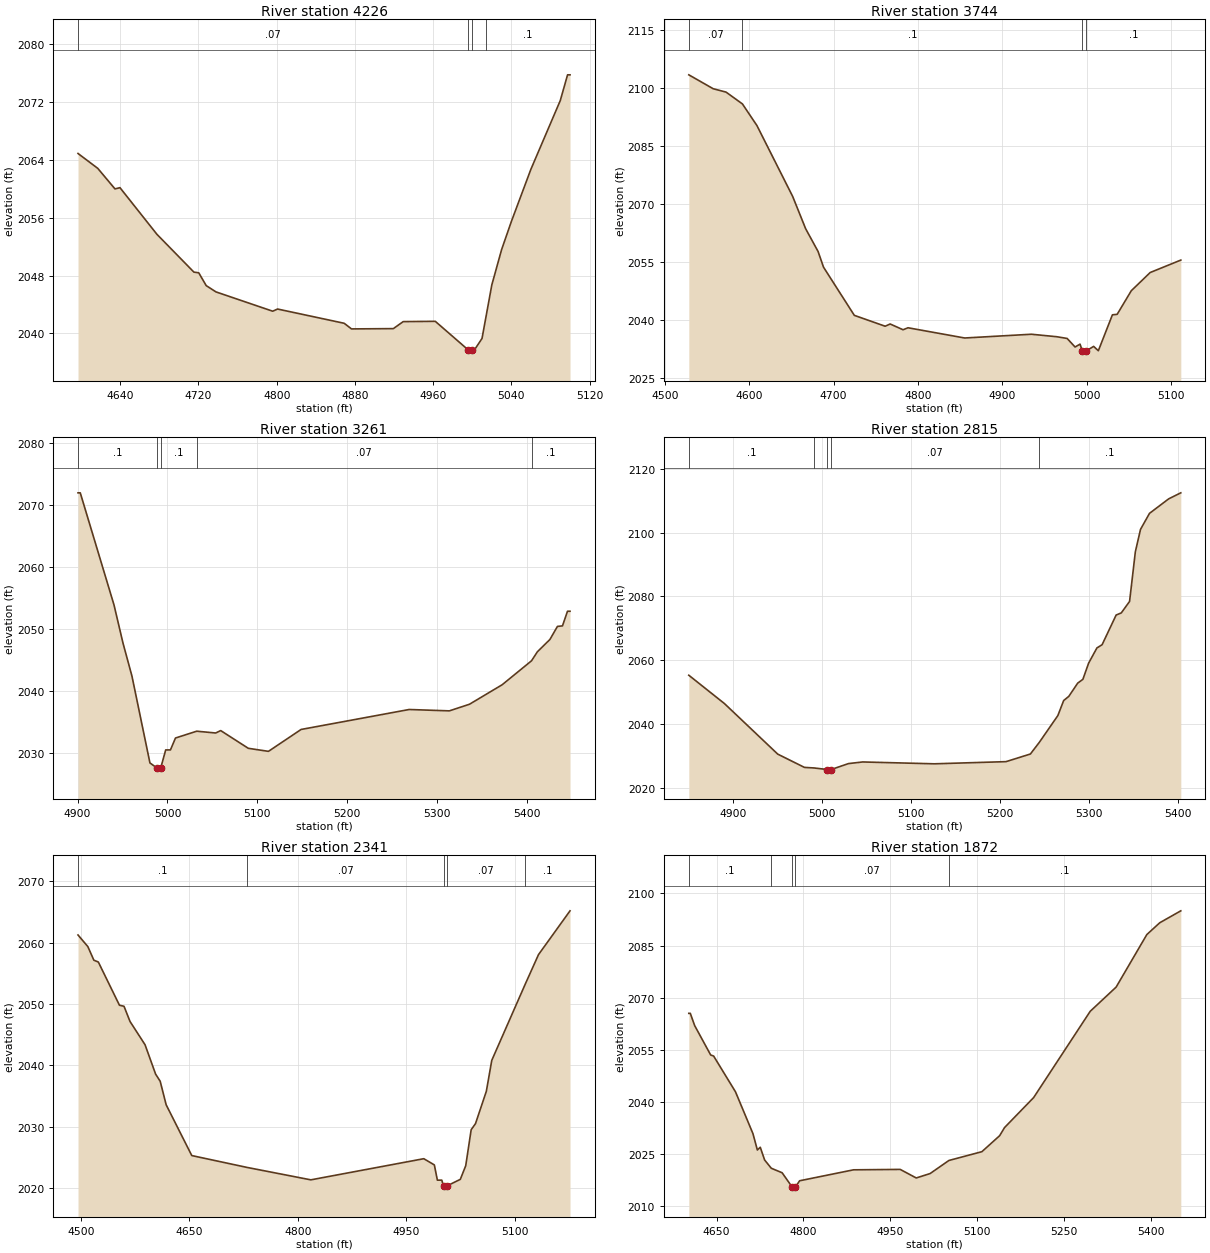
Type RM Length L Ch R = 1,4226,482,482,482
BEGIN DESCRIPTION:
Stream0284 7.0
END DESCRIPTION:
XS GIS Cut Line= 3
      1849574.95     13897775.01      1849975.00     13897725.00
      1850075.04     13897725.00
#Sta/Elev= 30
  4596.8 2064.89  4617.0 2062.83  4634.6 2059.99  4639.7 2060.16  4677.5 2053.71
  4715.3 2048.48  4720.3 2048.38  4727.9 2046.61  4737.9 2045.74  4795.9 2043.07
  4800.9 2043.37  4869.0 2041.40  4876.5 2040.62  4919.3 2040.66  4929.4 2041.63
  4962.2 2041.67  4995.4 2037.77  4995.7 2037.27  4999.2 2037.27  4999.4 2037.77
  5002.5 2037.77  5010.0 2039.30  5014.1 2042.33  5020.0 2046.70  5030.0 2051.58
  5040.0 2055.48  5060.0 2062.71  5090.0 2072.20  5097.5 2075.77  5100.0 2075.77
#Mann=4,-1,0
  4596.8    0.07       0  4995.4    0.05       0  4999.4    0.07       0
  5014.1     0.1       0
Bank Sta=4995.4,4999.4
Exp/Cntr=0.3,0.1

Type RM Length L Ch R = 1,3744,483,483,483
BEGIN DESCRIPTION:
Stream0284 6.0
END DESCRIPTION:
XS GIS Cut Line= 3
      1849475.00     13898425.00      1849875.00     13898175.00
      1849975.00     13898125.00
#Sta/Elev= 30
  4528.3 2103.37  4557.2 2099.78  4572.5 2098.90  4591.9 2095.85  4609.1 2090.26
  4651.5 2071.94  4666.9 2063.59  4681.6 2057.73  4688.1 2053.66  4724.6 2041.22
  4761.2 2038.41  4767.1 2038.99  4782.4 2037.50  4788.3 2038.01  4855.5 2035.37
  4934.6 2036.34  4964.6 2035.70  4977.0 2035.25  4986.4 2033.04  4992.3 2033.78
  4995.1 2031.96  4995.3 2031.46  4999.1 2031.96  5008.4 2033.20  5014.0 2032.08
  5030.7 2041.36  5036.3 2041.48  5053.1 2047.59  5075.5 2052.29  5111.8 2055.50
#Mann=4,-1,0
  4528.3    0.07       0  4591.9     0.1       0  4995.1    0.05       0
  4999.1     0.1       0
Bank Sta=4995.1,4999.1
Exp/Cntr=0.3,0.1

Type RM Length L Ch R = 1,3261,446,446,446
BEGIN DESCRIPTION:
Stream0284 5.0
END DESCRIPTION:
XS GIS Cut Line= 3
      1849675.01     13898625.00      1849775.00     13898625.00
      1850175.00     13898425.00
#Sta/Elev= 30
  4900.5 2072.04  4903.0 2072.04  4940.5 2053.97  4950.5 2047.82  4960.5 2042.47
  4980.5 2028.47  4988.4 2027.65  4988.7 2027.15  4992.3 2027.15  4992.5 2027.65
  4998.0 2030.57  5003.3 2030.57  5008.9 2032.49  5032.5 2033.59  5053.6 2033.30
  5059.2 2033.69  5089.9 2030.83  5112.3 2030.34  5148.6 2033.87  5268.8 2037.09
  5313.5 2036.87  5335.9 2037.94  5372.2 2041.08  5404.9 2044.95  5411.4 2046.40
  5425.3 2048.38  5433.7 2050.49  5439.3 2050.58  5444.9 2052.94  5447.7 2052.94
#Mann=5,-1,0
  4900.5     0.1       0  4988.4    0.05       0  4992.5     0.1       0
  5032.5    0.07       0  5404.9     0.1       0
Bank Sta=4988.4,4992.5
Exp/Cntr=0.3,0.1

Type RM Length L Ch R = 1,2815,474,474,474
BEGIN DESCRIPTION:
Stream0284 4.0
END DESCRIPTION:
XS GIS Cut Line= 3
      1849924.99     13898925.00      1850075.00     13898925.00
      1850424.98     13898725.01
#Sta/Elev= 30
  4850.3 2055.34  4890.3 2046.48  4950.3 2030.63  4980.3 2026.48  4991.1 2026.30
  5006.2 2025.81  5006.4 2025.31  5010.3 2025.81  5029.8 2027.67  5045.7 2028.18
  5126.3 2027.60  5206.9 2028.28  5234.3 2030.67  5244.3 2034.31  5265.2 2042.72
  5271.7 2047.41  5277.5 2048.73  5287.5 2052.87  5293.3 2054.05  5299.8 2059.15
  5309.1 2063.89  5314.9 2064.89  5330.7 2074.19  5336.5 2074.86  5345.8 2078.45
  5352.3 2094.01  5358.1 2101.01  5368.2 2106.03  5389.7 2110.56  5403.4 2112.46
#Mann=5,-1,0
  4850.3     0.1       0  4991.1    0.07       0  5006.2    0.05       0
  5010.3    0.07       0  5244.3     0.1       0
Bank Sta=5006.2,5010.3
Exp/Cntr=0.3,0.1

Type RM Length L Ch R = 1,2341,469,469,469
BEGIN DESCRIPTION:
Stream0284 3.0
END DESCRIPTION:
XS GIS Cut Line= 3
      1849924.99     13899575.01      1850325.00     13899275.00
      1850475.01     13899175.00
#Sta/Elev= 30
  4496.0 2061.23  4509.6 2059.34  4517.9 2057.13  4524.1 2056.83  4553.3 2049.80
  4559.6 2049.63  4567.9 2047.16  4588.7 2043.37  4603.3 2038.59  4609.6 2037.44
  4617.9 2033.60  4653.3 2025.34  4729.8 2023.41  4817.9 2021.39  4974.1 2024.83
  4988.7 2023.82  4992.9 2021.34  4999.0 2021.34  5001.4 2020.38  5001.7 2019.88
  5005.7 2020.38  5024.6 2021.47  5032.1 2023.69  5039.6 2029.54  5045.6 2030.54
  5060.6 2035.80  5068.1 2040.83  5114.0 2053.13  5132.7 2058.03  5176.3 2065.16
#Mann=5,-1,0
  4496.0     0.1       0  4729.8    0.07       0  5001.4    0.05       0
  5005.7    0.07       0  5114.0     0.1       0
Bank Sta=5001.4,5005.7
Exp/Cntr=0.3,0.1

Type RM Length L Ch R = 1,1872,440,440,440
BEGIN DESCRIPTION:
Stream0284 2.0
END DESCRIPTION:
XS GIS Cut Line= 3
      1849924.96     13899725.01      1850325.00     13899675.00
      1850725.03     13899875.01
#Sta/Elev= 30
  4601.9 2065.52  4604.5 2065.52  4612.0 2062.01  4639.7 2053.55  4644.8 2053.25
  4682.6 2042.96  4712.8 2030.92  4720.4 2026.23  4725.4 2027.02  4733.0 2023.34
  4744.5 2020.98  4763.2 2019.69  4780.9 2015.48  4781.2 2014.98  4785.8 2015.48
  4793.4 2017.38  4886.6 2020.53  4967.3 2020.65  4995.0 2018.19  5019.0 2019.46
  5051.5 2023.22  5108.5 2025.75  5139.2 2030.35  5147.6 2032.67  5197.9 2041.30
  5295.7 2066.11  5340.5 2073.07  5393.6 2088.18  5415.9 2091.57  5452.3 2095.00
#Mann=5,-1,0
  4601.9     0.1       0  4744.5    0.07       0  4780.9    0.05       0
  4785.8    0.07       0  5051.5     0.1       0
Bank Sta=4780.9,4785.8
Exp/Cntr=0.3,0.1

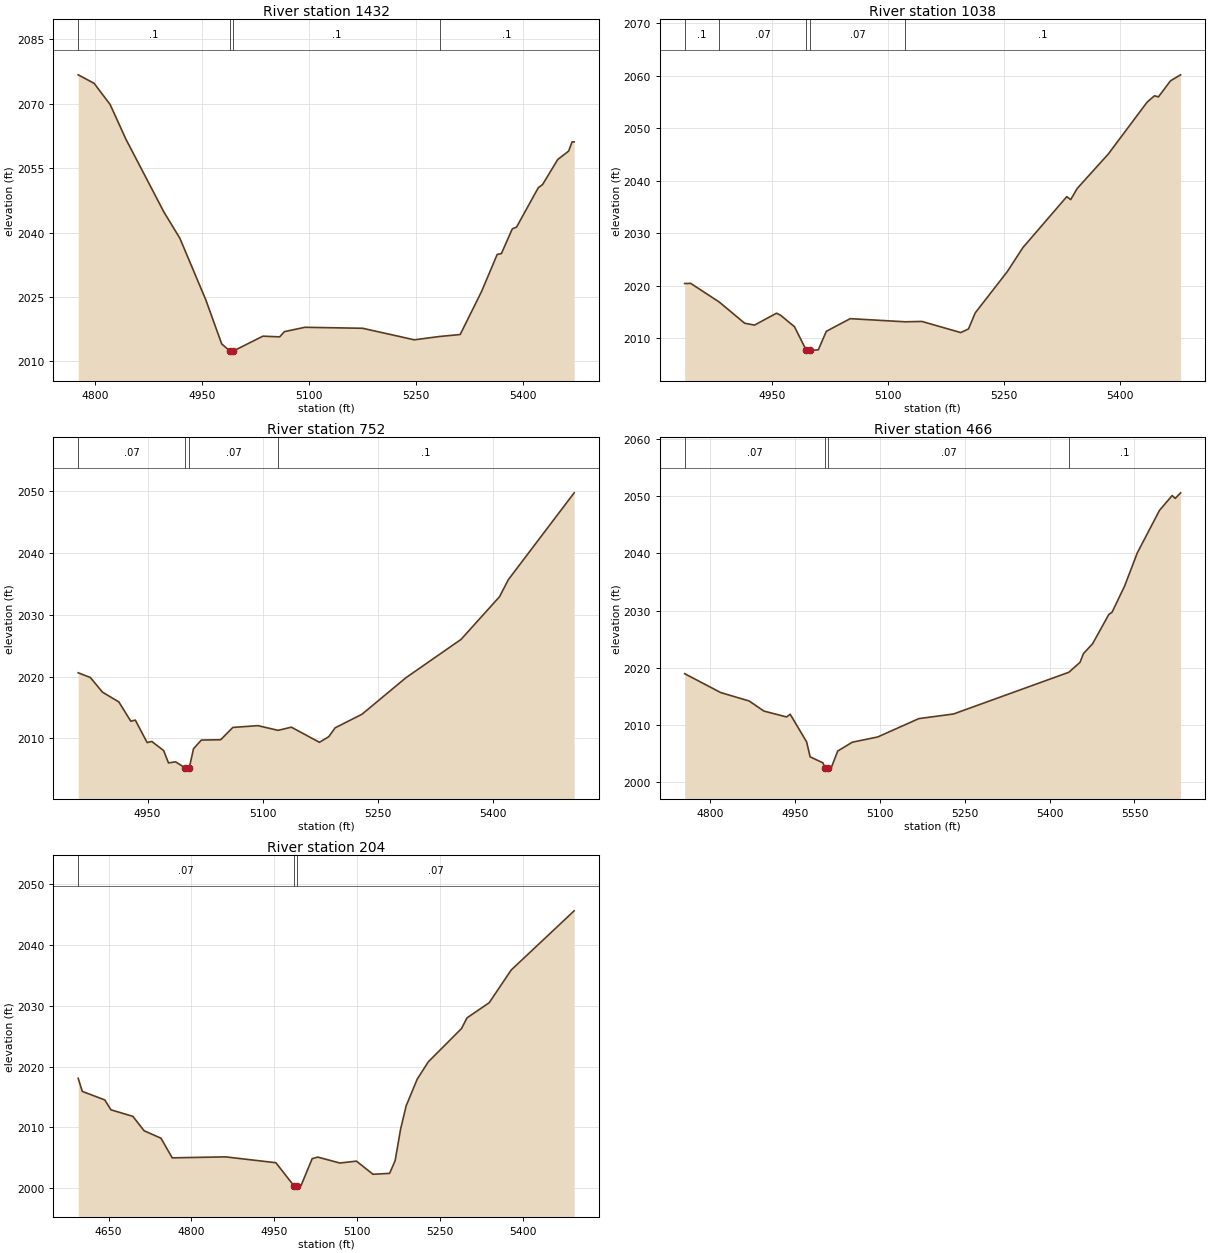
Type RM Length L Ch R = 1,1432,394,394,394
BEGIN DESCRIPTION:
Stream0284 1.0
END DESCRIPTION:
XS GIS Cut Line= 3
      1849825.04     13899875.02      1850025.00     13899975.00
      1850425.04     13900225.02
#Sta/Elev= 30
  4776.7 2076.75  4799.0 2074.77  4821.4 2069.85  4843.7 2061.72  4896.8 2044.81
  4919.2 2038.68  4955.5 2024.37  4977.9 2014.06  4989.4 2012.42  4989.8 2011.92
  4994.3 2012.42  5035.6 2015.87  5059.2 2015.71  5065.7 2016.92  5094.6 2017.94
  5175.4 2017.71  5247.9 2015.02  5283.4 2015.80  5312.2 2016.25  5342.2 2026.28
  5364.1 2034.91  5370.0 2035.11  5385.3 2040.88  5391.2 2041.27  5421.8 2050.47
  5427.7 2051.18  5449.0 2057.03  5464.3 2058.99  5469.0 2061.12  5472.0 2061.12
#Mann=4,-1,0
  4776.7     0.1       0  4989.4    0.05       0  4994.3     0.1       0
  5283.4     0.1       0
Bank Sta=4989.4,4994.3
Exp/Cntr=0.3,0.1

Type RM Length L Ch R = 1,1038,286,286,286
BEGIN DESCRIPTION:
Stream0284 0.0
END DESCRIPTION:
XS GIS Cut Line= 3
      1849817.50     13900310.46      1850106.69     13900383.03
      1850448.06     13900412.52
#Sta/Elev= 30
  4837.4 2020.43  4845.1 2020.47  4882.0 2016.92  4914.9 2012.88  4927.6 2012.52
  4956.1 2014.79  4961.2 2014.41  4979.2 2012.23  4994.7 2007.69  4995.1 2007.19
  4999.7 2007.69  5010.1 2007.82  5020.4 2011.34  5051.3 2013.75  5122.4 2013.15
  5143.9 2013.22  5194.1 2011.10  5204.1 2011.79  5212.8 2014.84  5254.3 2022.71
  5274.4 2027.27  5331.1 2036.96  5336.2 2036.40  5344.6 2038.52  5384.8 2045.08
  5435.0 2054.96  5444.5 2056.16  5449.5 2055.94  5465.1 2059.00  5478.2 2060.14
#Mann=5,-1,0
  4837.4     0.1       0  4882.0    0.07       0  4994.7    0.05       0
  4999.7    0.07       0  5122.4     0.1       0
Bank Sta=4994.7,4999.7
Exp/Cntr=0.3,0.1

Type RM Length L Ch R = 1,752,286,286,286
BEGIN DESCRIPTION:
Stream0284 0.1
END DESCRIPTION:
XS GIS Cut Line= 3
      1849804.16     13900553.13      1849918.23     13900621.33
      1850418.64     13900509.74
#Sta/Elev= 30
  4859.8 2020.61  4875.7 2019.84  4891.3 2017.49  4912.7 2015.90  4928.3 2012.78
  4934.1 2012.97  4949.6 2009.33  4955.5 2009.52  4971.0 2008.05  4977.3 2006.05
  4986.6 2006.22  4999.3 2005.22  4999.7 2004.72  5004.3 2005.22  5009.9 2008.34
  5020.1 2009.74  5045.2 2009.79  5061.1 2011.78  5093.8 2012.07  5119.9 2011.31
  5137.3 2011.82  5173.8 2009.38  5185.9 2010.28  5194.3 2011.72  5229.3 2013.92
  5286.5 2019.82  5358.2 2026.01  5408.3 2032.91  5419.7 2035.65  5505.4 2049.69
#Mann=4,-1,0
  4859.8    0.07       0  4999.3    0.05       0  5004.3    0.07       0
  5119.9     0.1       0
Bank Sta=4999.3,5004.3
Exp/Cntr=0.3,0.1

Type RM Length L Ch R = 1,466,262,262,262
BEGIN DESCRIPTION:
Stream0284 0.2
END DESCRIPTION:
XS GIS Cut Line= 4
      1849810.63     13900641.56      1849823.78     13900782.08
      1849906.46     13900888.27      1850444.27     13901156.28
#Sta/Elev= 30
  4755.0 2018.94  4818.7 2015.63  4868.9 2014.16  4895.1 2012.39  4935.2 2011.36
  4941.5 2011.84  4970.5 2007.00  4976.8 2004.37  4999.4 2003.32  5003.1 2002.37
  5003.5 2001.87  5008.3 2002.37  5013.9 2002.42  5025.5 2005.39  5051.4 2006.94
  5096.1 2007.85  5168.9 2011.07  5230.2 2011.88  5434.1 2019.19  5453.7 2020.92
  5459.9 2022.46  5476.0 2024.18  5504.7 2029.32  5510.3 2029.69  5532.6 2034.29
  5555.0 2040.09  5594.2 2047.54  5616.6 2050.14  5622.2 2049.65  5631.6 2050.62
#Mann=4,-1,0
  4755.0    0.07       0  5003.1    0.05       0  5008.3    0.07       0
  5434.1     0.1       0
Bank Sta=5003.1,5008.3
Exp/Cntr=0.3,0.1

Type RM Length L Ch R = 1,204,0,0,0
BEGIN DESCRIPTION:
Stream0284 0.3
END DESCRIPTION:
XS GIS Cut Line= 3
      1849780.44     13900637.76      1849712.75     13900989.38
      1849744.67     13901528.76
#Sta/Elev= 30
  4595.1 2018.07  4602.5 2015.92  4643.2 2014.52  4654.4 2012.89  4694.1 2011.82
  4714.5 2009.45  4745.0 2008.23  4765.4 2005.00  4862.0 2005.16  4953.2 2004.20
  4986.3 2000.36  4986.7 1999.86  4991.5 2000.36  4998.9 2000.47  5018.9 2004.86
  5028.9 2005.13  5069.0 2004.15  5099.1 2004.46  5129.1 2002.30  5159.2 2002.45
  5169.2 2004.54  5179.2 2009.77  5189.2 2013.55  5209.2 2017.93  5229.3 2020.78
  5289.4 2026.24  5299.4 2028.00  5339.5 2030.48  5379.5 2035.87  5493.5 2045.59
#Mann=3,-1,0
  4595.1    0.07       0  4986.3    0.05       0  4991.5    0.07       0
Bank Sta=4986.3,4991.5
Exp/Cntr=0.3,0.1

Chan Stop Cuts=-1