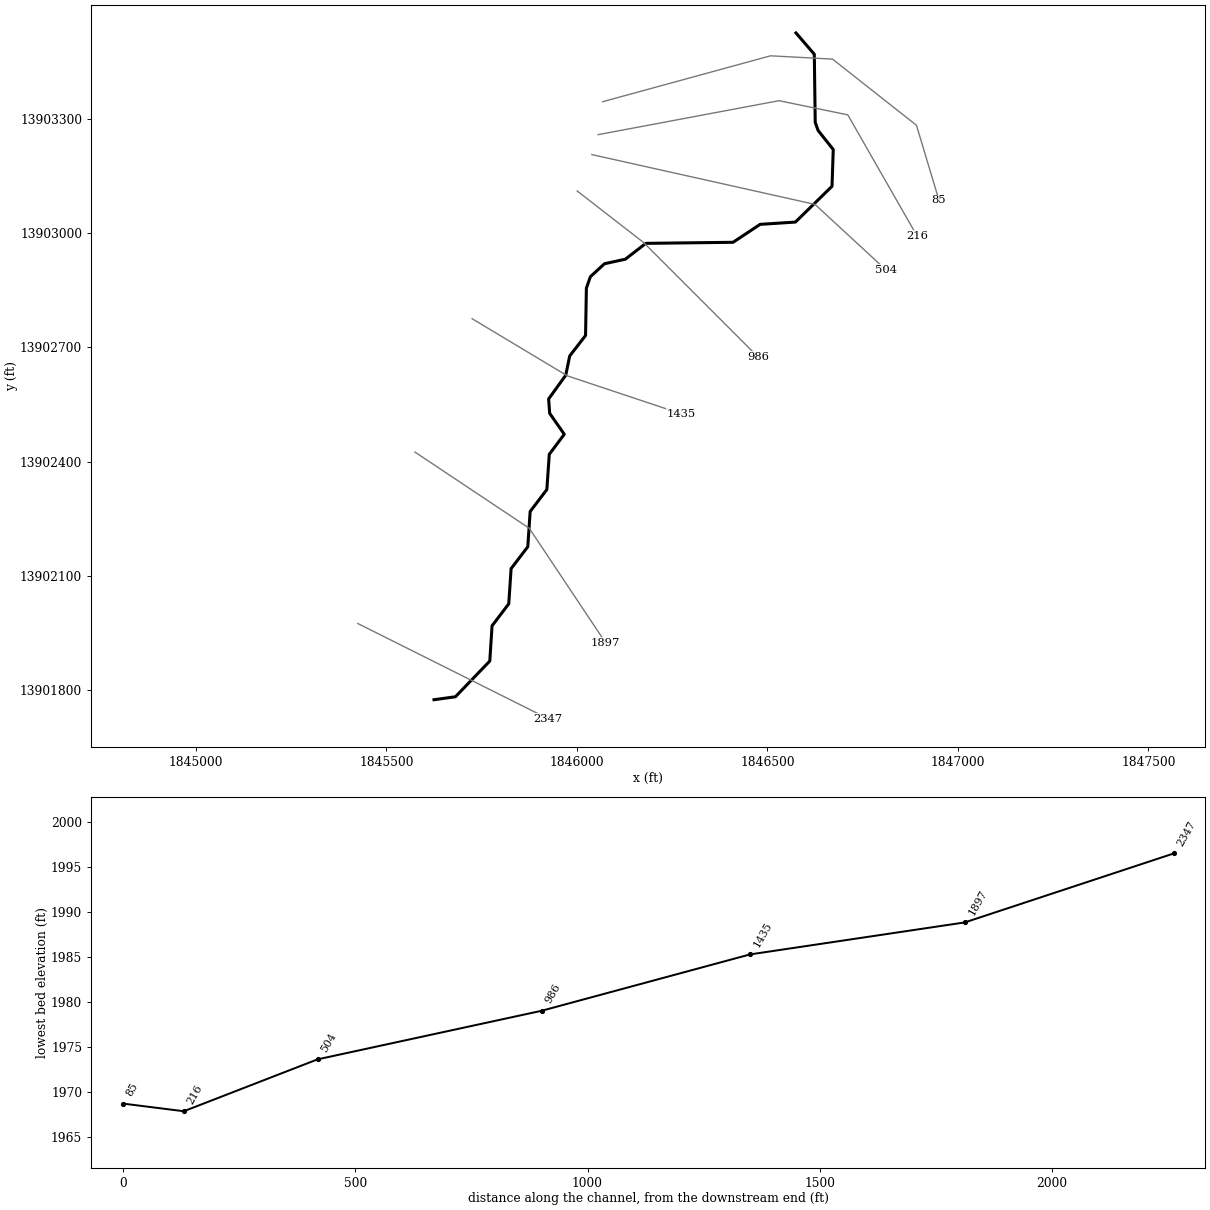
--- Stream0286.prj (project) ---

Proj Title=Stream0286 Base Level Engineering
Current Plan=p01
Default Exp/Contr=0.3,0.1
English Units
Geom File=g01
Flow File=f01
Plan File=p01
BEGIN DESCRIPTION:
Stream0286
END DESCRIPTION:

--- Stream0286.p01 (plan) ---

Plan Title=Multiple Run
Short Identifier=Multiple
Geom File=g01
Flow File=f01
Subcritical Flow
K Sum by GR= 0
Std Step Tol= 0.01
Critical Tol= 0.01
Num of Std Step Trials= 20
Max Error Tol= 0.3
Flow Tol Ratio= 0.001
Split Flow NTrial= 30
Split Flow Tol= 0.02
Split Flow Ratio= 0.02
Log Output Level= 0
Friction Slope Method= 1
Unsteady Friction Slope Method= 2
Unsteady Bridges Friction Slope Method= 1
Parabolic Critical Depth
Global Vel Dist=  1 , 1 , 1
Global Log Level= 0
CheckData=True
Encroach Param= -1, 0, 0, 0
BEGIN DESCRIPTION:
Multiple Run
END DESCRIPTION:

--- Stream0286.f01 (steady flow) ---

Flow Title=Multiple
Number of Profiles=7
Profile Names=10-year,25-year,50-year,1pct_min,100-year,1pct_plu,500-year
River Rch & RM= Stream0286,Reach-1,2347
    1131    1951    2739    1860    3710    7403    6732
Boundary for River Rch & Prof#=Stream0286,Reach-1,1
Up Type=0
Dn Type=3
Dn Slope=0.005
Boundary for River Rch & Prof#=Stream0286,Reach-1,2
Up Type=0
Dn Type=3
Dn Slope=0.005
Boundary for River Rch & Prof#=Stream0286,Reach-1,3
Up Type=0
Dn Type=3
Dn Slope=0.005
Boundary for River Rch & Prof#=Stream0286,Reach-1,4
Up Type=0
Dn Type=3
Dn Slope=0.005
Boundary for River Rch & Prof#=Stream0286,Reach-1,5
Up Type=0
Dn Type=3
Dn Slope=0.005
Boundary for River Rch & Prof#=Stream0286,Reach-1,6
Up Type=0
Dn Type=3
Dn Slope=0.005
Boundary for River Rch & Prof#=Stream0286,Reach-1,7
Up Type=0
Dn Type=3
Dn Slope=0.005

--- Stream0286.g01 (geometry) ---

Geom Title=Existing Conditions

River Reach=Stream0286,Reach-1
Reach XY= 30
      1845625.00     13901775.00      1845681.24     13901782.75
      1845771.40     13901876.48      1845777.36     13901969.02
      1845821.15     13902026.60      1845827.35     13902119.03
      1845871.15     13902176.60      1845877.35     13902269.03
      1845921.15     13902326.60      1845927.55     13902419.11
      1845966.90     13902471.71      1845928.60     13902526.64
      1845925.80     13902564.30      1845970.78     13902626.72
      1845981.11     13902677.18      1846022.75     13902730.93
      1846024.93     13902855.11      1846035.35     13902885.12
      1846072.41     13902919.29      1846127.14     13902931.15
      1846180.93     13902972.76      1846409.78     13902975.52
      1846480.98     13903022.64      1846573.52     13903028.61
      1846669.61     13903122.56      1846672.84     13903219.02
      1846633.15     13903268.94      1846625.52     13903290.22
      1846623.11     13903469.22      1846575.00     13903525.00

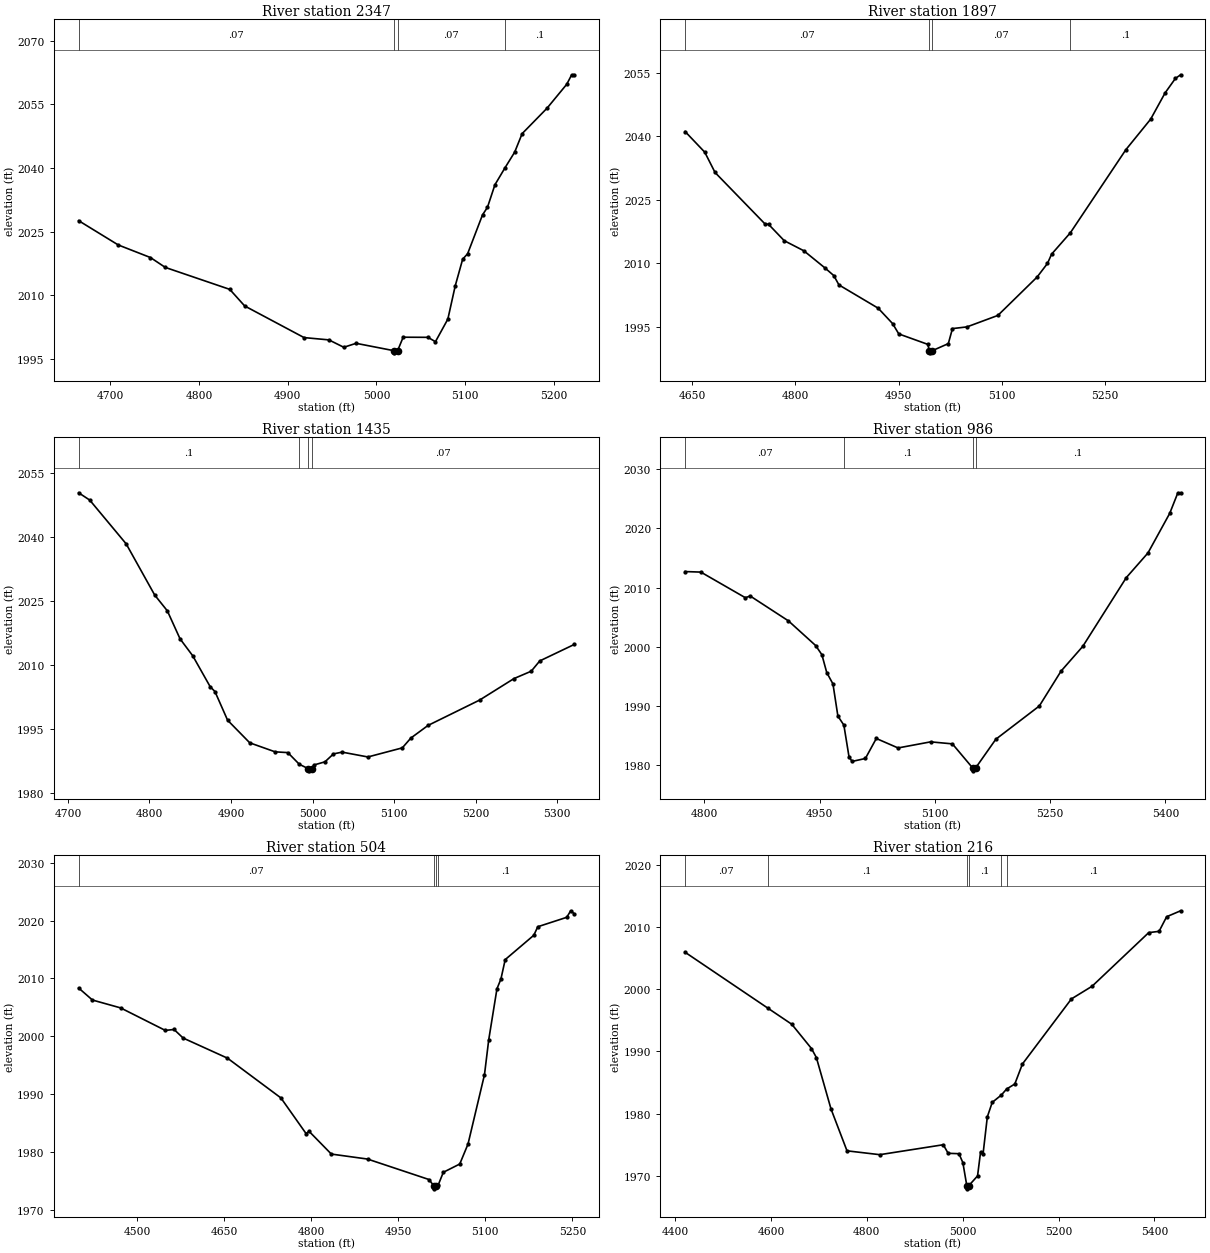
Type RM Length L Ch R = 1,2347,450,450,450
BEGIN DESCRIPTION:
Stream0286 5.0
END DESCRIPTION:
XS GIS Cut Line= 3
      1845425.01     13901975.00      1845725.00     13901825.00
      1845924.99     13901725.00
#Sta/Elev= 30
  4664.1 2027.61  4708.8 2021.89  4745.1 2018.93  4761.9 2016.60  4834.6 2011.43
  4851.4 2007.53  4918.4 2000.08  4946.4 1999.54  4963.2 1997.80  4977.1 1998.73
  5019.9 1996.99  5020.1 1996.49  5023.9 1996.99  5030.2 2000.17  5058.2 2000.14
  5066.6 1999.11  5080.6 2004.43  5088.9 2012.24  5097.3 2018.53  5102.9 2019.82
  5119.7 2028.97  5125.3 2030.76  5133.7 2036.06  5144.9 2040.00  5156.0 2043.75
  5164.4 2048.10  5192.4 2054.07  5214.7 2059.72  5220.3 2061.96  5223.1 2061.96
#Mann=4,-1,0
  4664.1    0.07       0  5019.9    0.05       0  5023.9    0.07       0
  5144.9     0.1       0
Bank Sta=5019.9,5023.9
Exp/Cntr=0.3,0.1

Type RM Length L Ch R = 1,1897,462,462,462
BEGIN DESCRIPTION:
Stream0286 4.0
END DESCRIPTION:
XS GIS Cut Line= 3
      1845574.96     13902425.02      1845875.00     13902225.00
      1846075.02     13901924.96
#Sta/Elev= 30
  4639.4 2041.13  4668.0 2036.25  4683.0 2031.45  4755.1 2019.39  4761.1 2019.16
  4783.7 2015.33  4812.2 2012.95  4842.3 2008.98  4855.8 2007.09  4863.3 2004.88
  4920.4 1999.38  4941.4 1995.74  4950.4 1993.30  4992.5 1990.84  4995.0 1989.33
  4995.2 1988.83  4999.0 1989.33  5022.5 1991.01  5028.5 1994.56  5049.6 1994.96
  5094.6 1997.67  5151.7 2006.74  5166.8 2009.96  5172.8 2012.15  5200.1 2017.20
  5280.9 2036.84  5317.0 2044.06  5338.0 2050.26  5353.0 2053.68  5360.6 2054.54
#Mann=4,-1,0
  4639.4    0.07       0  4995.0    0.05       0  4999.0    0.07       0
  5200.1     0.1       0
Bank Sta=4995,4999
Exp/Cntr=0.3,0.1

Type RM Length L Ch R = 1,1435,449,449,449
BEGIN DESCRIPTION:
Stream0286 3.0
END DESCRIPTION:
XS GIS Cut Line= 3
      1845725.00     13902775.00      1845975.00     13902625.00
      1846275.02     13902524.99
#Sta/Elev= 30
  4713.1 2050.40  4726.7 2048.69  4771.4 2038.44  4806.4 2026.45  4821.9 2022.75
  4837.5 2016.19  4853.0 2012.24  4874.4 2005.00  4880.3 2003.85  4895.8 1997.14
  4923.0 1991.84  4954.1 1989.73  4969.7 1989.55  4983.8 1986.81  4994.9 1985.78
  4995.1 1985.28  4998.9 1985.78  5001.7 1986.65  5015.2 1987.39  5025.7 1989.25
  5036.3 1989.66  5067.9 1988.53  5110.1 1990.66  5120.6 1992.96  5141.7 1995.92
  5204.9 2001.85  5247.1 2006.89  5268.2 2008.61  5278.7 2011.02  5320.9 2014.87
#Mann=4,-1,0
  4713.1     0.1       0  4983.8    0.07       0  4994.9    0.05       0
  4998.9    0.07       0
Bank Sta=4994.9,4998.9
Exp/Cntr=0.3,0.1

Type RM Length L Ch R = 1,986,482,482,482
BEGIN DESCRIPTION:
Stream0286 2.0
END DESCRIPTION:
XS GIS Cut Line= 3
      1846000.80     13903110.18      1846175.00     13902975.00
      1846475.03     13902674.97
#Sta/Elev= 30
  4775.0 2012.71  4795.5 2012.62  4853.4 2008.29  4859.7 2008.58  4909.5 2004.37
  4944.9 2000.20  4953.0 1998.65  4959.3 1995.64  4967.4 1993.71  4973.8 1988.28
  4981.6 1986.75  4988.3 1981.38  4992.3 1980.61  5009.6 1981.11  5023.8 1984.49
  5052.1 1982.89  5094.5 1983.92  5122.8 1983.58  5149.1 1979.52  5149.3 1979.02
  5153.1 1979.52  5179.3 1984.36  5235.9 1989.98  5264.2 1995.88  5292.5 2000.07
  5349.1 2011.69  5377.3 2015.86  5405.6 2022.55  5416.2 2026.03  5419.8 2026.03
#Mann=4,-1,0
  4775.0    0.07       0  4981.6     0.1       0  5149.1    0.05       0
  5153.1     0.1       0
Bank Sta=5149.1,5153.1
Exp/Cntr=0.3,0.1

Type RM Length L Ch R = 1,504,288,288,288
BEGIN DESCRIPTION:
Stream0286 1.0
END DESCRIPTION:
XS GIS Cut Line= 3
      1846039.30     13903205.74      1846625.00     13903075.00
      1846811.24     13902903.04
#Sta/Elev= 30
  4399.4 2008.35  4423.2 2006.27  4471.7 2004.91  4548.7 2001.02  4563.8 2001.18
  4579.4 1999.70  4655.8 1996.22  4747.8 1989.35  4791.2 1983.18  4796.3 1983.58
  4834.7 1979.64  4897.0 1978.78  5002.9 1975.24  5011.4 1974.13  5011.7 1973.63
  5015.4 1974.13  5018.6 1974.24  5027.6 1976.49  5055.9 1977.92  5070.1 1981.36
  5098.5 1993.36  5105.8 1999.39  5120.0 2008.22  5126.8 2009.89  5134.2 2013.26
  5183.5 2017.47  5190.3 2018.94  5240.2 2020.57  5247.0 2021.70  5253.0 2021.20
#Mann=4,-1,0
  4399.4    0.07       0  5011.4    0.05       0  5015.4    0.07       0
  5018.6     0.1       0
Bank Sta=5011.4,5015.4
Exp/Cntr=0.3,0.1

Type RM Length L Ch R = 1,216,131,131,131
BEGIN DESCRIPTION:
Stream0286 0.0
END DESCRIPTION:
XS GIS Cut Line= 4
      1846055.92     13903258.08      1846530.49     13903347.20
      1846711.00     13903309.99      1846892.94     13902991.91
#Sta/Elev= 30
  4421.0 2005.96  4592.9 1997.00  4643.5 1994.37  4684.6 1990.46  4694.8 1989.01
  4725.3 1980.74  4758.7 1973.99  4827.1 1973.37  4959.5 1974.97  4969.7 1973.59
  4992.2 1973.53  5000.4 1972.08  5008.6 1968.37  5008.8 1967.87  5012.6 1968.37
  5031.0 1969.95  5037.3 1973.80  5042.4 1973.43  5051.4 1979.46  5061.6 1981.79
  5080.6 1982.97  5091.6 1983.94  5108.7 1984.75  5124.6 1987.97  5226.8 1998.45
  5269.9 2000.49  5388.0 2009.12  5409.6 2009.33  5425.4 2011.68  5454.6 2012.64
#Mann=6,-1,0
  4421.0    0.07       0  4592.9     0.1       0  5008.6    0.05       0
  5012.6     0.1       0  5080.6    0.07       0  5091.6     0.1       0
Bank Sta=5008.6,5012.6
Exp/Cntr=0.3,0.1

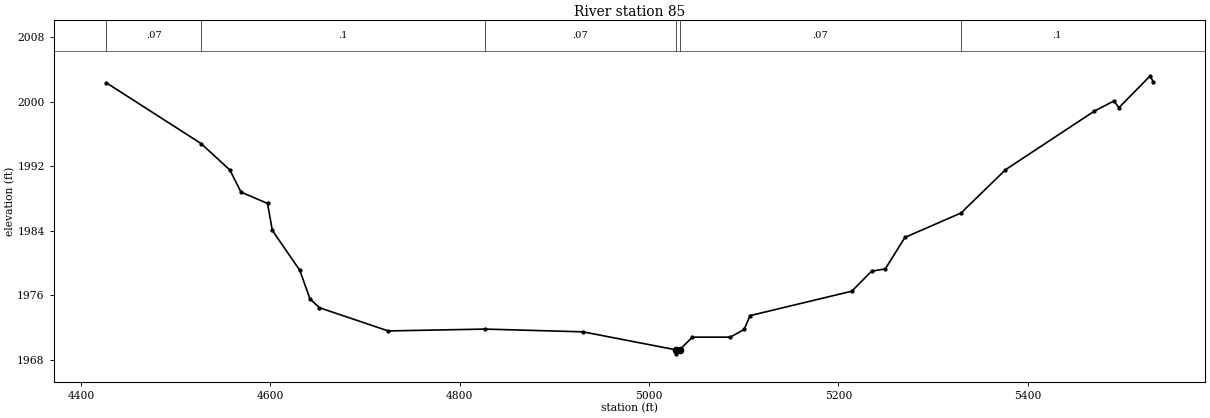
Type RM Length L Ch R = 1,85,0,0,0
BEGIN DESCRIPTION:
Stream0286 0.1
END DESCRIPTION:
XS GIS Cut Line= 5
      1846067.66     13903344.53      1846508.21     13903464.97
      1846670.97     13903456.29      1846891.24     13903282.68
      1846950.45     13903085.66
#Sta/Elev= 30
  4426.6 2002.34  4526.8 1994.80  4557.3 1991.51  4569.0 1988.78  4597.0 1987.37
  4602.1 1984.03  4631.2 1979.06  4641.8 1975.54  4651.9 1974.44  4724.5 1971.56
  4826.7 1971.79  4930.2 1971.45  5028.3 1969.22  5028.6 1968.72  5032.3 1969.22
  5045.8 1970.79  5086.0 1970.79  5100.5 1971.75  5106.8 1973.46  5214.3 1976.49
  5235.1 1978.97  5249.6 1979.25  5270.4 1983.16  5329.7 1986.19  5376.6 1991.55
  5470.5 1998.82  5491.2 2000.08  5496.4 1999.24  5529.5 2003.20  5532.5 2002.47
#Mann=6,-1,0
  4426.6    0.07       0  4526.8     0.1       0  4826.7    0.07       0
  5028.3    0.05       0  5032.3    0.07       0  5329.7     0.1       0
Bank Sta=5028.3,5032.3
Exp/Cntr=0.3,0.1

Chan Stop Cuts=-1