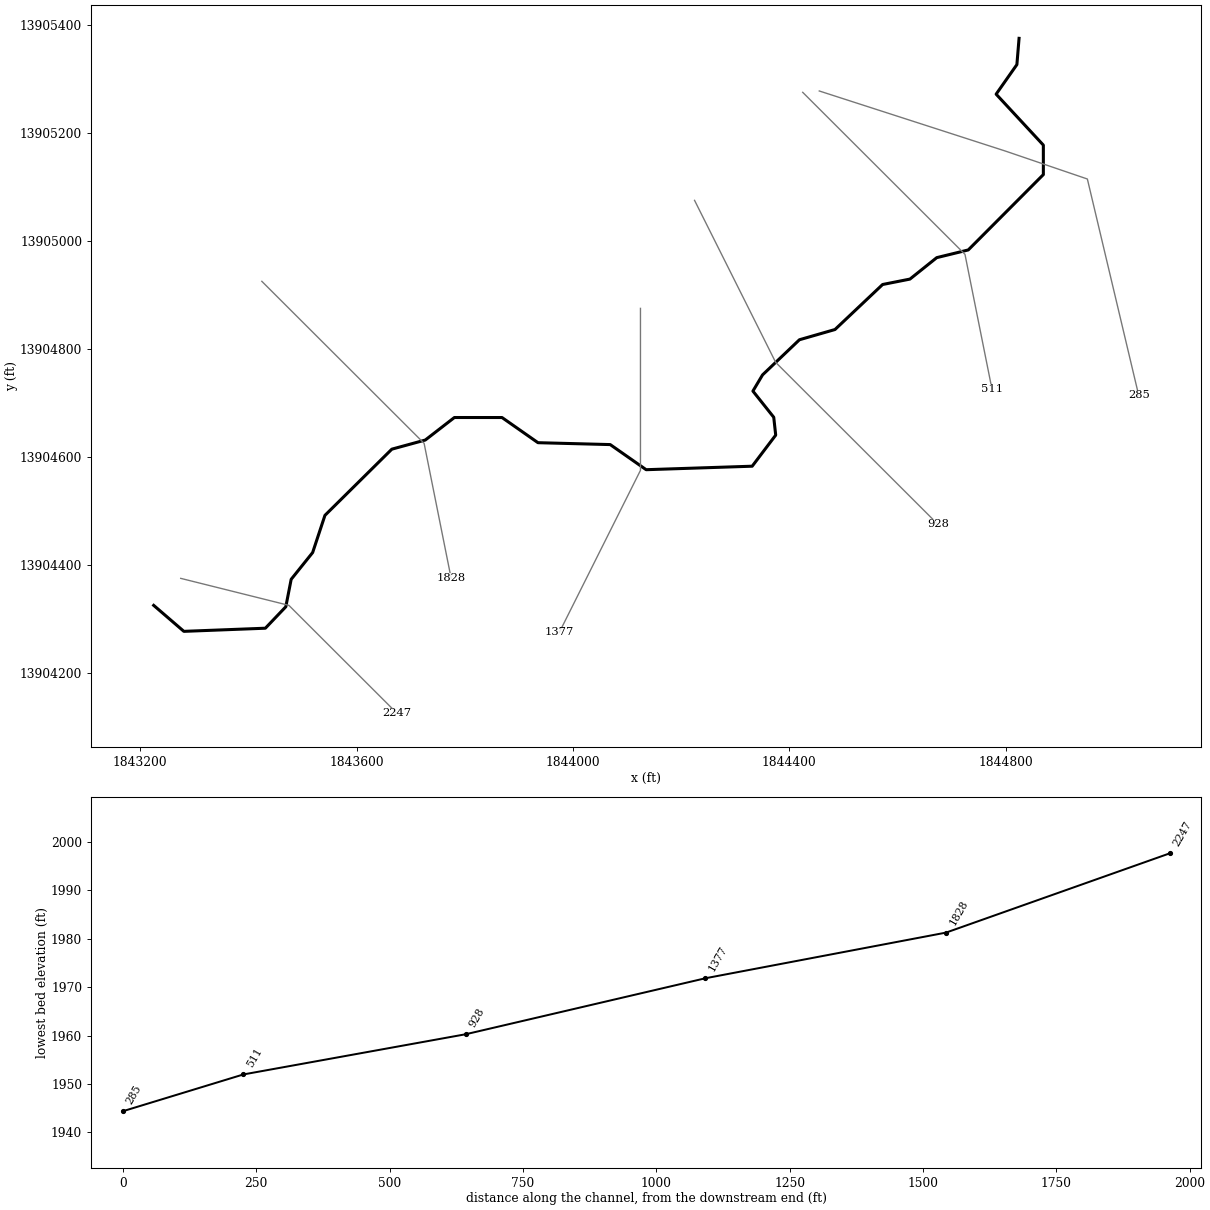
--- Stream0287.prj (project) ---

Proj Title=Stream0287 Base Level Engineering
Current Plan=p01
Default Exp/Contr=0.3,0.1
English Units
Geom File=g01
Flow File=f01
Plan File=p01
BEGIN DESCRIPTION:
Stream0287
END DESCRIPTION:

--- Stream0287.p01 (plan) ---

Plan Title=Multiple Run
Short Identifier=Multiple
Geom File=g01
Flow File=f01
Subcritical Flow
K Sum by GR= 0
Std Step Tol= 0.01
Critical Tol= 0.01
Num of Std Step Trials= 20
Max Error Tol= 0.3
Flow Tol Ratio= 0.001
Split Flow NTrial= 30
Split Flow Tol= 0.02
Split Flow Ratio= 0.02
Log Output Level= 0
Friction Slope Method= 1
Unsteady Friction Slope Method= 2
Unsteady Bridges Friction Slope Method= 1
Parabolic Critical Depth
Global Vel Dist=  1 , 1 , 1
Global Log Level= 0
CheckData=True
Encroach Param= -1, 0, 0, 0
BEGIN DESCRIPTION:
Multiple Run
END DESCRIPTION:

--- Stream0287.f01 (steady flow) ---

Flow Title=Multiple
Number of Profiles=7
Profile Names=10-year,25-year,50-year,1pct_min,100-year,1pct_plu,500-year
River Rch & RM= Stream0287,Reach-1,2247
     630    1055    1454     973    1942    3874    3413
Boundary for River Rch & Prof#=Stream0287,Reach-1,1
Up Type=0
Dn Type=3
Dn Slope=0.005
Boundary for River Rch & Prof#=Stream0287,Reach-1,2
Up Type=0
Dn Type=3
Dn Slope=0.005
Boundary for River Rch & Prof#=Stream0287,Reach-1,3
Up Type=0
Dn Type=3
Dn Slope=0.005
Boundary for River Rch & Prof#=Stream0287,Reach-1,4
Up Type=0
Dn Type=3
Dn Slope=0.005
Boundary for River Rch & Prof#=Stream0287,Reach-1,5
Up Type=0
Dn Type=3
Dn Slope=0.005
Boundary for River Rch & Prof#=Stream0287,Reach-1,6
Up Type=0
Dn Type=3
Dn Slope=0.005
Boundary for River Rch & Prof#=Stream0287,Reach-1,7
Up Type=0
Dn Type=3
Dn Slope=0.005

--- Stream0287.g01 (geometry) ---

Geom Title=Existing Conditions

River Reach=Stream0287,Reach-1
Reach XY= 30
      1843225.00     13904325.00      1843280.79     13904276.88
      1843431.48     13904282.69      1843469.29     13904322.41
      1843479.20     13904373.23      1843518.90     13904422.81
      1843541.64     13904491.68      1843665.32     13904614.24
      1843727.17     13904631.15      1843780.97     13904672.86
      1843869.02     13904672.83      1843935.51     13904626.23
      1844069.06     13904622.73      1844135.51     13904576.22
      1844331.57     13904582.69      1844375.05     13904640.22
      1844371.43     13904673.32      1844332.91     13904721.78
      1844350.70     13904751.75      1844418.91     13904816.84
      1844484.67     13904835.80      1844572.71     13904919.15
      1844623.27     13904929.19      1844672.81     13904968.90
      1844731.06     13904983.14      1844869.93     13905122.71
      1844869.91     13905177.29      1844782.60     13905271.62
      1844820.98     13905326.36      1844825.00     13905375.00

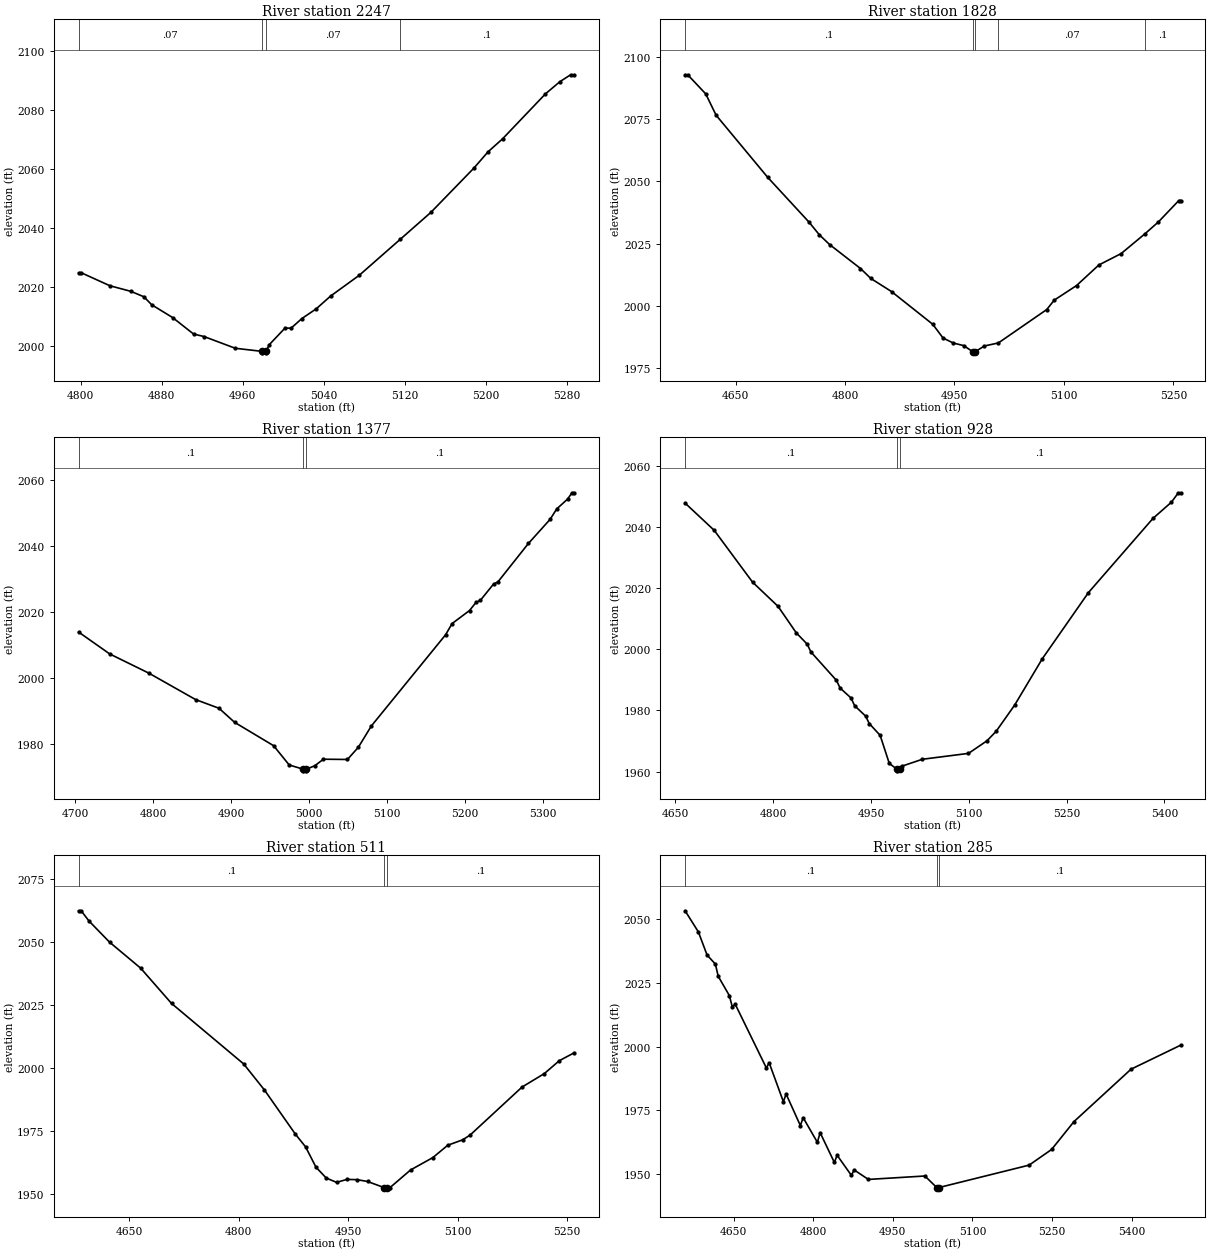
Type RM Length L Ch R = 1,2247,419,419,419
BEGIN DESCRIPTION:
Stream0287 5.0
END DESCRIPTION:
XS GIS Cut Line= 3
      1843275.01     13904375.00      1843475.00     13904325.00
      1843675.01     13904124.99
#Sta/Elev= 30
  4798.0 2024.82  4800.6 2024.82  4828.9 2020.41  4849.5 2018.52  4862.4 2016.67
  4870.1 2013.96  4890.8 2009.60  4911.4 2004.02  4921.7 2003.17  4952.6 1999.18
  4979.0 1998.13  4979.2 1997.63  4982.7 1997.63  4983.0 1998.13  4986.1 2000.39
  5001.6 2006.02  5007.7 2006.02  5018.3 2009.28  5032.4 2012.56  5046.6 2016.90
  5074.9 2023.96  5115.2 2036.13  5145.6 2045.33  5188.0 2060.35  5202.1 2065.93
  5216.3 2070.29  5258.7 2085.59  5272.8 2089.69  5283.5 2092.06  5287.0 2092.06
#Mann=4,-1,0
  4798.0    0.07       0  4979.0    0.05       0  4983.0    0.07       0
  5115.2     0.1       0
Bank Sta=4979,4983
Exp/Cntr=0.3,0.1

Type RM Length L Ch R = 1,1828,451,451,451
BEGIN DESCRIPTION:
Stream0287 4.0
END DESCRIPTION:
XS GIS Cut Line= 3
      1843424.98     13904925.02      1843725.00     13904625.00
      1843774.99     13904375.04
#Sta/Elev= 30
  4580.8 2092.74  4584.4 2092.74  4609.1 2085.07  4623.3 2076.53  4694.0 2051.63
  4750.5 2033.72  4764.7 2028.63  4778.8 2024.70  4821.2 2015.08  4835.4 2011.08
  4863.7 2005.84  4920.2 1992.73  4934.4 1987.19  4948.5 1985.19  4962.7 1984.17
  4974.8 1981.77  4975.1 1981.27  4978.6 1981.27  4978.8 1981.77  4990.9 1984.01
  5010.2 1985.24  5076.5 1998.63  5086.7 2002.38  5117.3 2008.24  5147.9 2016.49
  5178.5 2021.07  5211.0 2028.97  5229.4 2033.71  5257.5 2042.32  5260.0 2042.32
#Mann=5,-1,0
  4580.8     0.1       0  4974.8    0.05       0  4978.8     0.1       0
  5010.2    0.07       0  5211.0     0.1       0
Bank Sta=4974.8,4978.8
Exp/Cntr=0.3,0.1

Type RM Length L Ch R = 1,1377,449,449,449
BEGIN DESCRIPTION:
Stream0287 3.0
END DESCRIPTION:
XS GIS Cut Line= 3
      1844125.00     13904874.97      1844125.00     13904575.00
      1843974.99     13904274.98
#Sta/Elev= 30
  4704.6 2013.96  4744.6 2007.30  4794.6 2001.50  4854.6 1993.47  4884.6 1990.83
  4904.6 1986.56  4954.6 1979.47  4974.6 1973.62  4992.6 1972.34  4992.8 1971.84
  4996.3 1971.84  4996.6 1972.34  5007.4 1973.39  5018.5 1975.37  5049.3 1975.29
  5063.3 1979.01  5080.0 1985.48  5175.1 2013.13  5183.5 2016.55  5205.8 2020.50
  5214.2 2022.98  5219.8 2023.61  5236.6 2028.53  5242.2 2029.18  5281.3 2040.85
  5309.2 2048.19  5317.6 2051.33  5331.6 2054.34  5337.2 2056.24  5340.0 2056.24
#Mann=3,-1,0
  4704.6     0.1       0  4992.6    0.05       0  4996.6     0.1       0
Bank Sta=4992.6,4996.6
Exp/Cntr=0.3,0.1

Type RM Length L Ch R = 1,928,417,417,417
BEGIN DESCRIPTION:
Stream0287 2.0
END DESCRIPTION:
XS GIS Cut Line= 3
      1844225.01     13905074.98      1844375.00     13904775.00
      1844674.97     13904475.03
#Sta/Elev= 30
  4665.2 2047.73  4709.9 2038.82  4768.6 2021.91  4807.7 2014.00  4835.7 2005.33
  4852.4 2001.65  4858.0 1999.13  4897.2 1989.82  4902.8 1987.32  4919.5 1984.09
  4925.1 1981.55  4941.9 1978.16  4947.5 1975.73  4964.2 1971.86  4978.2 1962.70
  4990.2 1960.78  4990.4 1960.28  4994.2 1960.78  4997.8 1961.82  5028.9 1964.06
  5099.6 1965.98  5127.9 1970.08  5142.0 1973.19  5170.3 1981.73  5212.7 1996.87
  5283.4 2018.48  5382.4 2042.73  5410.7 2048.03  5421.3 2051.10  5424.8 2051.10
#Mann=3,-1,0
  4665.2     0.1       0  4990.2    0.05       0  4994.2     0.1       0
Bank Sta=4990.2,4994.2
Exp/Cntr=0.3,0.1

Type RM Length L Ch R = 1,511,226,226,226
BEGIN DESCRIPTION:
Stream0287 1.0
END DESCRIPTION:
XS GIS Cut Line= 3
      1844424.99     13905275.01      1844725.00     13904975.00
      1844775.00     13904725.02
#Sta/Elev= 30
  4580.5 2062.47  4584.0 2062.47  4594.6 2058.44  4622.9 2050.00  4665.4 2039.70
  4707.8 2025.66  4806.8 2001.58  4835.1 1991.28  4877.5 1973.74  4891.6 1968.63
  4905.8 1960.58  4919.9 1956.26  4934.1 1954.54  4948.2 1955.72  4962.3 1955.61
  4976.5 1954.89  4999.2 1952.47  4999.5 1951.97  5003.0 1951.97  5003.2 1952.47
  5007.3 1952.47  5035.4 1959.46  5066.0 1964.39  5086.4 1969.29  5106.8 1971.44
  5117.0 1973.32  5188.3 1992.43  5218.9 1997.79  5239.3 2002.89  5259.7 2006.03
#Mann=3,-1,0
  4580.5     0.1       0  4999.2    0.05       0  5003.2     0.1       0
Bank Sta=4999.2,5003.2
Exp/Cntr=0.3,0.1

Type RM Length L Ch R = 1,285,0,0,0
BEGIN DESCRIPTION:
Stream0287 0.0
END DESCRIPTION:
XS GIS Cut Line= 4
      1844455.63     13905277.51      1844799.15     13905166.44
      1844951.29     13905114.51      1845046.19     13904713.99
#Sta/Elev= 30
  4558.7 2053.06  4583.7 2044.80  4600.1 2035.76  4615.7 2032.23  4621.1 2027.46
  4642.1 2019.89  4647.7 2015.41  4653.0 2016.59  4711.8 1991.61  4717.0 1993.68
  4743.8 1978.43  4749.0 1981.43  4775.8 1969.10  4781.1 1972.18  4807.8 1962.57
  4813.1 1966.31  4839.8 1954.70  4845.1 1957.48  4871.9 1949.64  4877.1 1951.77
  4903.9 1948.05  5010.4 1949.39  5032.7 1944.87  5032.9 1944.37  5036.7 1944.87
  5206.7 1953.64  5249.0 1959.75  5291.2 1970.66  5398.6 1991.13  5492.1 2000.52
#Mann=3,-1,0
  4558.7     0.1       0  5032.7    0.05       0  5036.7     0.1       0
Bank Sta=5032.7,5036.7
Exp/Cntr=0.3,0.1

Chan Stop Cuts=-1