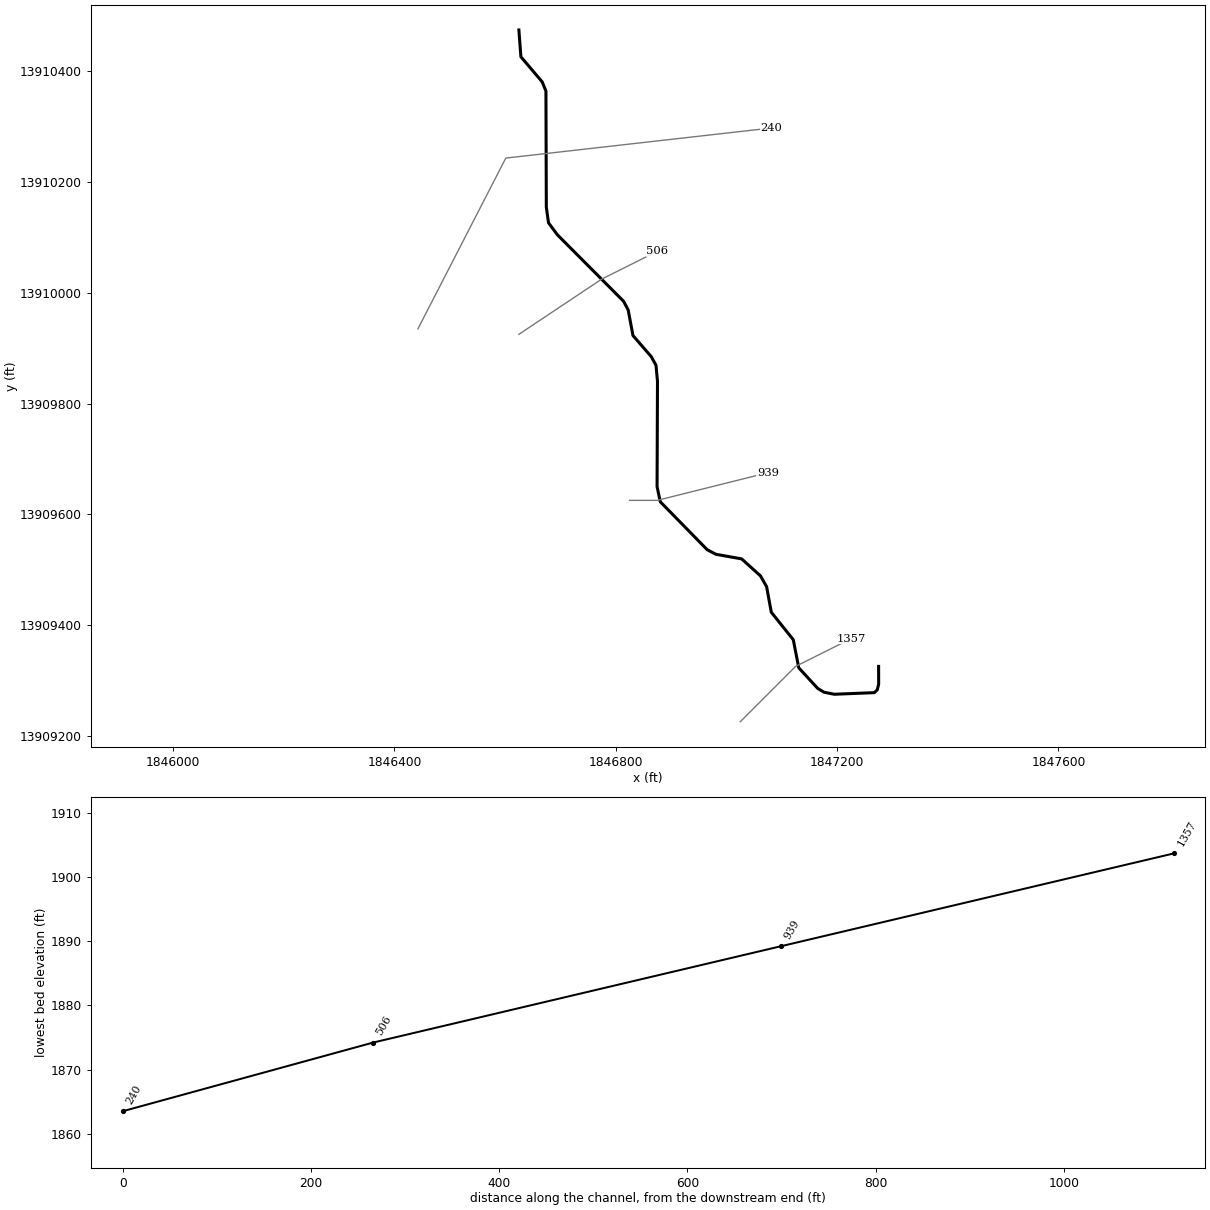
--- Stream0288.prj (project) ---

Proj Title=Stream0288 Base Level Engineering
Current Plan=p01
Default Exp/Contr=0.3,0.1
English Units
Geom File=g01
Flow File=f01
Plan File=p01
BEGIN DESCRIPTION:
Stream0288
END DESCRIPTION:

--- Stream0288.p01 (plan) ---

Plan Title=Multiple Run
Short Identifier=Multiple
Geom File=g01
Flow File=f01
Subcritical Flow
K Sum by GR= 0
Std Step Tol= 0.01
Critical Tol= 0.01
Num of Std Step Trials= 20
Max Error Tol= 0.3
Flow Tol Ratio= 0.001
Split Flow NTrial= 30
Split Flow Tol= 0.02
Split Flow Ratio= 0.02
Log Output Level= 0
Friction Slope Method= 1
Unsteady Friction Slope Method= 2
Unsteady Bridges Friction Slope Method= 1
Parabolic Critical Depth
Global Vel Dist=  1 , 1 , 1
Global Log Level= 0
CheckData=True
Encroach Param= -1, 0, 0, 0
BEGIN DESCRIPTION:
Multiple Run
END DESCRIPTION:

--- Stream0288.f01 (steady flow) ---

Flow Title=Multiple
Number of Profiles=7
Profile Names=10-year,25-year,50-year,1pct_min,100-year,1pct_plu,500-year
River Rch & RM= Stream0288,Reach-1,1357
     473     778    1059     702    1400    2793    2406
Boundary for River Rch & Prof#=Stream0288,Reach-1,1
Up Type=0
Dn Type=3
Dn Slope=0.005
Boundary for River Rch & Prof#=Stream0288,Reach-1,2
Up Type=0
Dn Type=3
Dn Slope=0.005
Boundary for River Rch & Prof#=Stream0288,Reach-1,3
Up Type=0
Dn Type=3
Dn Slope=0.005
Boundary for River Rch & Prof#=Stream0288,Reach-1,4
Up Type=0
Dn Type=3
Dn Slope=0.005
Boundary for River Rch & Prof#=Stream0288,Reach-1,5
Up Type=0
Dn Type=3
Dn Slope=0.005
Boundary for River Rch & Prof#=Stream0288,Reach-1,6
Up Type=0
Dn Type=3
Dn Slope=0.005
Boundary for River Rch & Prof#=Stream0288,Reach-1,7
Up Type=0
Dn Type=3
Dn Slope=0.005

--- Stream0288.g01 (geometry) ---

Geom Title=Existing Conditions

River Reach=Stream0288,Reach-1
Reach XY= 30
      1847275.00     13909325.00      1847275.08     13909292.99
      1847272.59     13909282.72      1847267.23     13909277.56
      1847195.01     13909274.67      1847176.30     13909278.33
      1847164.91     13909285.29      1847130.72     13909322.41
      1847120.80     13909373.23      1847081.11     13909422.84
      1847072.58     13909469.15      1847061.53     13909488.57
      1847027.54     13909519.25      1846981.08     13909527.55
      1846965.31     13909535.78      1846880.45     13909622.53
      1846874.70     13909649.87      1846875.44     13909840.18
      1846872.76     13909869.07      1846864.21     13909884.67
      1846831.14     13909922.83      1846822.50     13909968.97
      1846814.24     13909984.68      1846694.61     13910104.84
      1846678.54     13910126.46      1846674.57     13910154.82
      1846673.88     13910364.54      1846667.11     13910381.16
      1846628.65     13910426.51      1846625.00     13910475.00

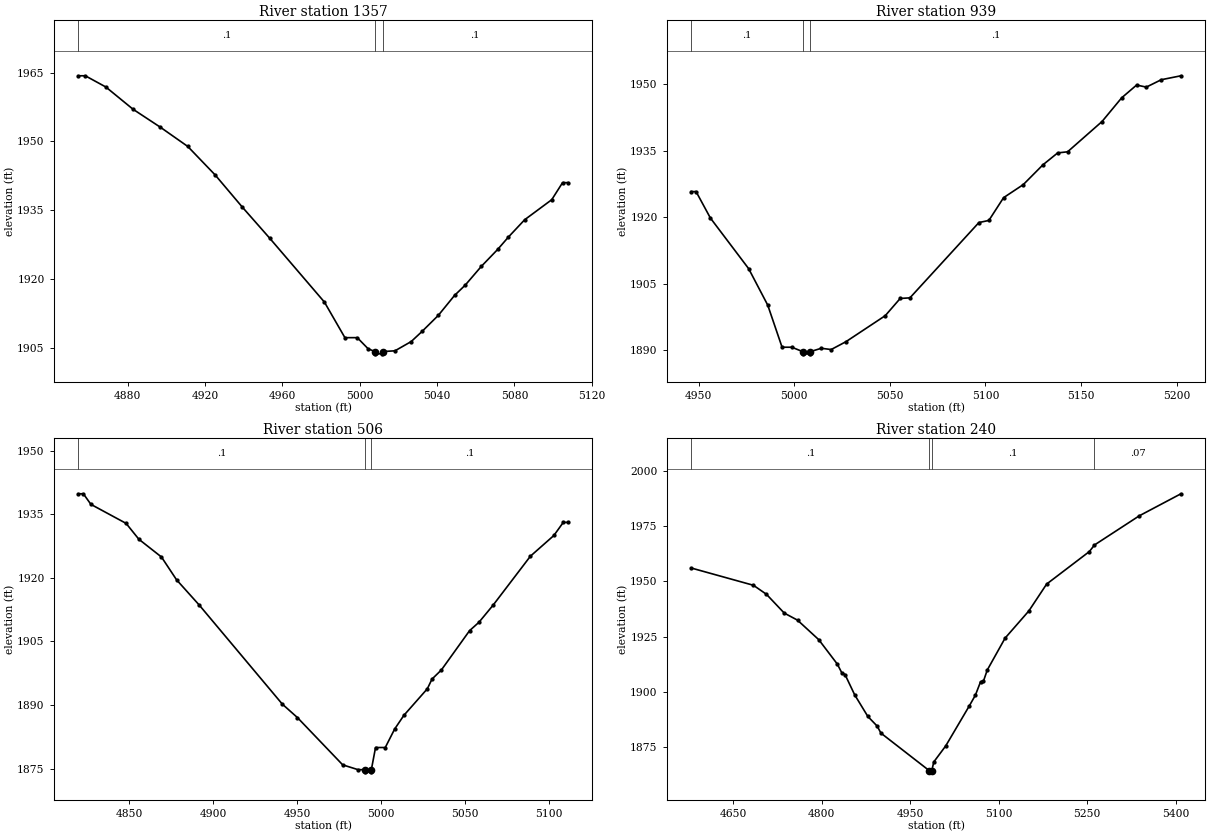
Type RM Length L Ch R = 1,1357,418,418,418
BEGIN DESCRIPTION:
Stream0288 3.0
END DESCRIPTION:
XS GIS Cut Line= 3
      1847024.97     13909224.97      1847125.00     13909325.00
      1847225.03     13909375.01
#Sta/Elev= 30
  4854.4 1964.33  4858.0 1964.33  4868.6 1961.89  4882.7 1957.03  4896.9 1953.09
  4911.0 1948.92  4925.2 1942.69  4939.3 1935.65  4953.4 1928.90  4981.7 1914.97
  4992.3 1907.21  4998.7 1907.21  5004.3 1904.79  5007.8 1904.18  5008.1 1903.68
  5011.6 1903.68  5011.8 1904.18  5018.2 1904.34  5026.6 1906.36  5032.2 1908.56
  5040.6 1912.06  5049.0 1916.41  5054.6 1918.69  5062.9 1922.77  5071.3 1926.44
  5076.9 1929.16  5085.3 1932.93  5099.3 1937.30  5104.9 1941.02  5107.7 1941.02
#Mann=3,-1,0
  4854.4     0.1       0  5007.8    0.05       0  5011.8     0.1       0
Bank Sta=5007.8,5011.8
Exp/Cntr=0.3,0.1

Type RM Length L Ch R = 1,939,433,433,433
BEGIN DESCRIPTION:
Stream0288 2.0
END DESCRIPTION:
XS GIS Cut Line= 3
      1846825.00     13909625.00      1846875.00     13909625.00
      1847075.04     13909675.01
#Sta/Elev= 30
  4946.1 1925.75  4948.6 1925.75  4956.1 1919.79  4976.1 1908.40  4986.1 1900.18
  4993.6 1890.70  4998.7 1890.70  5004.4 1889.71  5004.7 1889.21  5008.2 1889.21
  5008.4 1889.71  5014.1 1890.46  5019.3 1890.18  5027.0 1891.94  5047.6 1897.81
  5055.4 1901.68  5060.5 1901.82  5096.6 1918.78  5101.8 1919.25  5109.5 1924.38
  5119.8 1927.32  5130.1 1931.78  5137.8 1934.46  5143.0 1934.71  5161.0 1941.52
  5171.3 1946.87  5179.1 1949.74  5184.2 1949.28  5192.0 1950.94  5202.3 1951.83
#Mann=3,-1,0
  4946.1     0.1       0  5004.4    0.05       0  5008.4     0.1       0
Bank Sta=5004.4,5008.4
Exp/Cntr=0.3,0.1

Type RM Length L Ch R = 1,506,266,266,266
BEGIN DESCRIPTION:
Stream0288 1.0
END DESCRIPTION:
XS GIS Cut Line= 3
      1846625.00     13909925.00      1846775.00     13910025.00
      1846875.02     13910075.01
#Sta/Elev= 30
  4819.5 1939.86  4822.5 1939.86  4827.0 1937.36  4848.0 1932.87  4855.6 1929.13
  4869.1 1924.93  4878.1 1919.55  4891.6 1913.60  4941.2 1890.20  4950.2 1887.03
  4977.2 1875.87  4986.3 1874.74  4990.3 1874.72  4990.5 1874.22  4994.0 1874.22
  4994.3 1874.72  4996.8 1879.96  5002.6 1879.96  5008.2 1884.32  5013.7 1887.55
  5027.7 1893.83  5030.5 1896.12  5036.1 1898.28  5052.9 1907.55  5058.5 1909.53
  5066.9 1913.55  5089.2 1925.13  5103.2 1930.02  5108.8 1933.11  5111.6 1933.11
#Mann=3,-1,0
  4819.5     0.1       0  4990.3    0.05       0  4994.3     0.1       0
Bank Sta=4990.3,4994.3
Exp/Cntr=0.3,0.1

Type RM Length L Ch R = 1,240,0,0,0
BEGIN DESCRIPTION:
Stream0288 0.0
END DESCRIPTION:
XS GIS Cut Line= 3
      1846442.58     13909934.93      1846601.36     13910243.46
      1847081.10     13910297.82
#Sta/Elev= 30
  4578.9 1956.12  4684.2 1948.28  4706.3 1944.18  4736.4 1935.66  4758.9 1932.44
  4795.0 1923.55  4826.4 1912.47  4833.8 1908.61  4839.4 1907.74  4855.9 1898.46
  4878.1 1888.69  4893.9 1884.31  4900.3 1881.12  4982.4 1864.03  4982.7 1863.53
  4986.4 1864.03  4989.9 1868.04  5010.1 1875.32  5050.3 1893.60  5060.4 1898.38
  5069.1 1904.43  5074.1 1904.79  5080.5 1909.79  5110.7 1924.28  5151.0 1936.64
  5181.1 1948.83  5253.5 1963.60  5262.2 1966.59  5338.2 1979.85  5408.7 1989.85
#Mann=4,-1,0
  4578.9     0.1       0  4982.4    0.05       0  4986.4     0.1       0
  5262.2    0.07       0
Bank Sta=4982.4,4986.4
Exp/Cntr=0.3,0.1

Chan Stop Cuts=-1