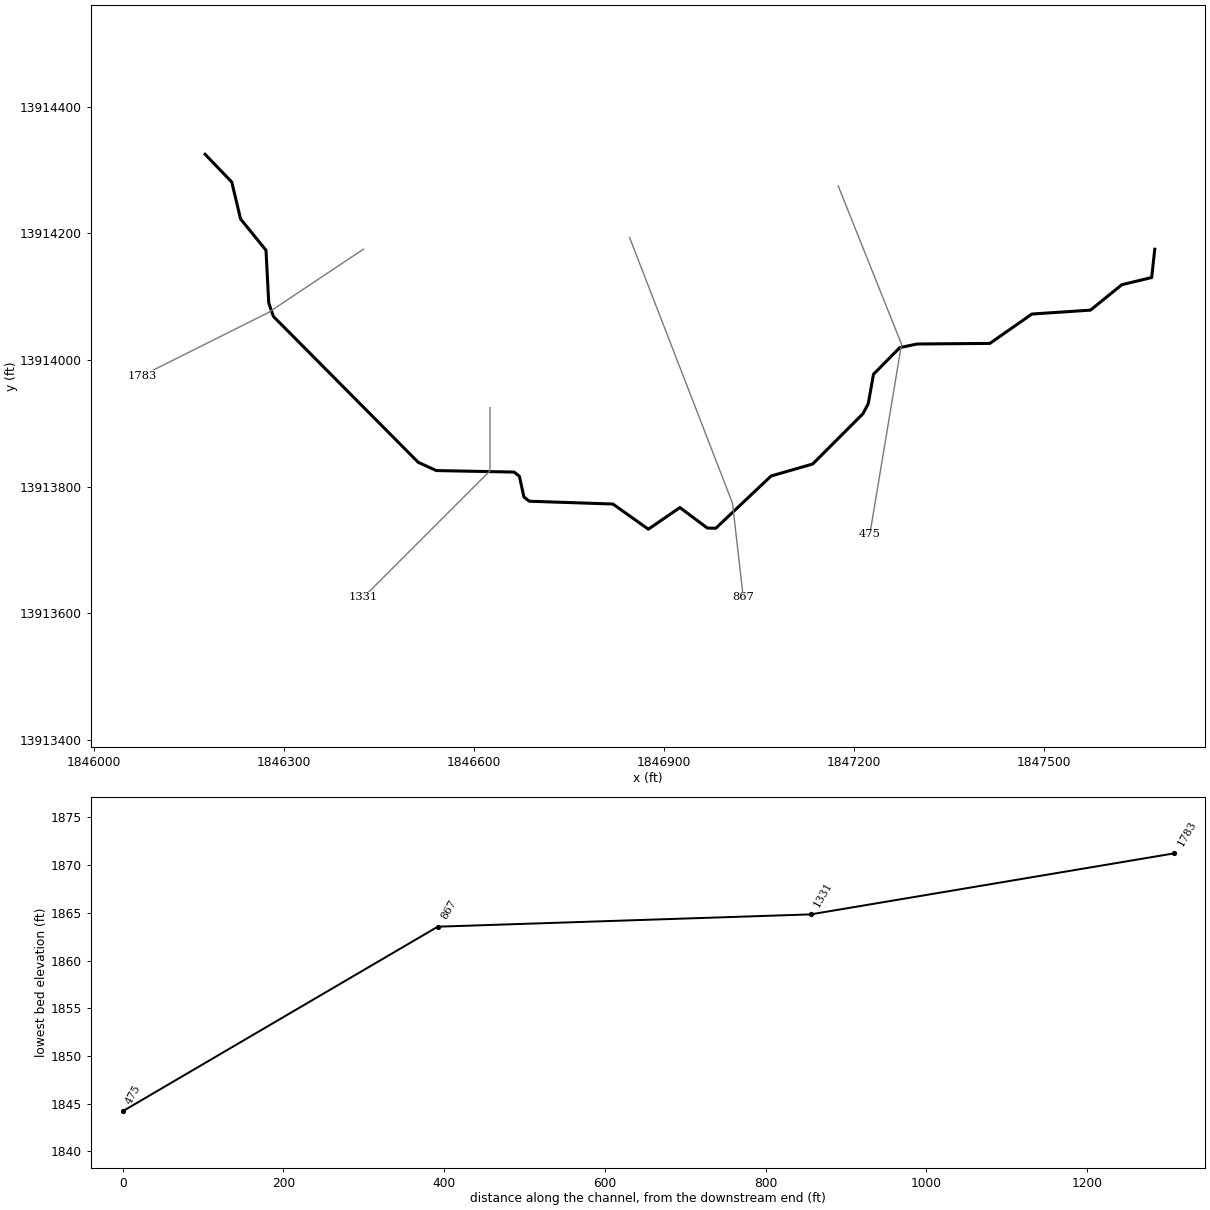
--- Stream0289.prj (project) ---

Proj Title=Stream0289 Base Level Engineering
Current Plan=p01
Default Exp/Contr=0.3,0.1
English Units
Geom File=g01
Flow File=f01
Plan File=p01
BEGIN DESCRIPTION:
Stream0289
END DESCRIPTION:

--- Stream0289.p01 (plan) ---

Plan Title=Multiple Run
Short Identifier=Multiple
Geom File=g01
Flow File=f01
Subcritical Flow
K Sum by GR= 0
Std Step Tol= 0.01
Critical Tol= 0.01
Num of Std Step Trials= 20
Max Error Tol= 0.3
Flow Tol Ratio= 0.001
Split Flow NTrial= 30
Split Flow Tol= 0.02
Split Flow Ratio= 0.02
Log Output Level= 0
Friction Slope Method= 1
Unsteady Friction Slope Method= 2
Unsteady Bridges Friction Slope Method= 1
Parabolic Critical Depth
Global Vel Dist=  1 , 1 , 1
Global Log Level= 0
CheckData=True
Encroach Param= -1, 0, 0, 0
BEGIN DESCRIPTION:
Multiple Run
END DESCRIPTION:

--- Stream0289.f01 (steady flow) ---

Flow Title=Multiple
Number of Profiles=7
Profile Names=10-year,25-year,50-year,1pct_min,100-year,1pct_plu,500-year
River Rch & RM= Stream0289,Reach-1,1783
    1521    2671    3795    2605    5198   10372    9642
Boundary for River Rch & Prof#=Stream0289,Reach-1,1
Up Type=0
Dn Type=3
Dn Slope=0.005
Boundary for River Rch & Prof#=Stream0289,Reach-1,2
Up Type=0
Dn Type=3
Dn Slope=0.005
Boundary for River Rch & Prof#=Stream0289,Reach-1,3
Up Type=0
Dn Type=3
Dn Slope=0.005
Boundary for River Rch & Prof#=Stream0289,Reach-1,4
Up Type=0
Dn Type=3
Dn Slope=0.005
Boundary for River Rch & Prof#=Stream0289,Reach-1,5
Up Type=0
Dn Type=3
Dn Slope=0.005
Boundary for River Rch & Prof#=Stream0289,Reach-1,6
Up Type=0
Dn Type=3
Dn Slope=0.005
Boundary for River Rch & Prof#=Stream0289,Reach-1,7
Up Type=0
Dn Type=3
Dn Slope=0.005

--- Stream0289.g01 (geometry) ---

Geom Title=Existing Conditions

River Reach=Stream0289,Reach-1
Reach XY= 30
      1846175.00     13914325.00      1846217.09     13914281.15
      1846231.03     13914222.78      1846271.18     13914173.42
      1846275.52     13914090.22      1846282.86     13914068.83
      1846511.69     13913838.37      1846540.18     13913825.40
      1846663.03     13913823.02      1846671.41     13913816.41
      1846678.59     13913783.59      1846686.97     13913776.98
      1846819.14     13913772.54      1846875.10     13913732.78
      1846925.00     13913766.96      1846968.33     13913734.59
      1846981.66     13913734.31      1847068.95     13913816.80
      1847134.70     13913835.77      1847214.22     13913915.32
      1847222.45     13913931.08      1847230.74     13913977.57
      1847272.30     13914019.64      1847299.80     13914025.31
      1847414.49     13914026.23      1847480.98     13914072.65
      1847573.45     13914078.79      1847623.00     13914118.96
      1847670.10     13914130.28      1847675.00     13914175.00

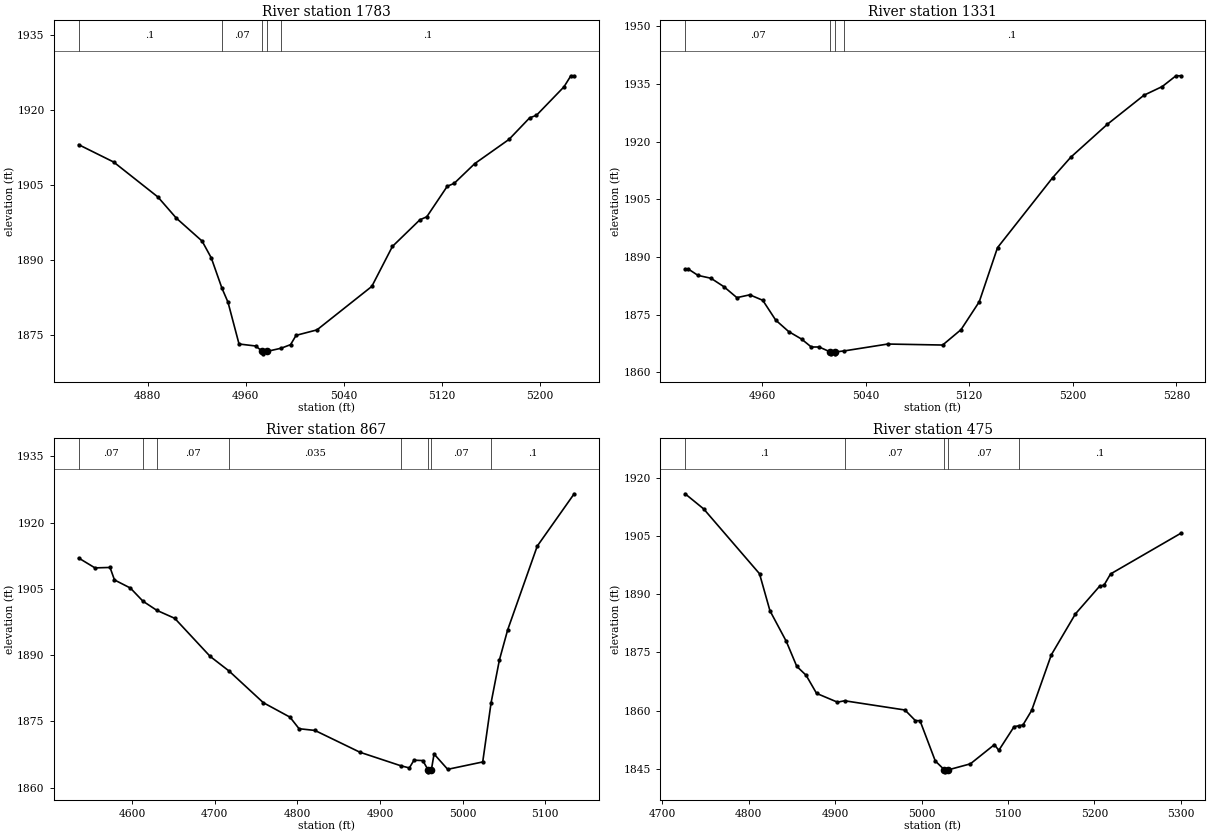
Type RM Length L Ch R = 1,1783,452,452,452
BEGIN DESCRIPTION:
Stream0289 4.0
END DESCRIPTION:
XS GIS Cut Line= 3
      1846424.97     13914174.98      1846275.00     13914075.00
      1846075.04     13913975.02
#Sta/Elev= 30
  4823.8 1913.08  4852.3 1909.61  4888.4 1902.61  4903.4 1898.38  4924.4 1893.79
  4931.9 1890.42  4940.6 1884.35  4945.5 1881.57  4954.5 1873.20  4968.0 1872.80
  4973.5 1871.73  4973.7 1871.23  4977.5 1871.73  4988.9 1872.36  4996.5 1873.07
  5001.0 1874.93  5018.0 1876.02  5062.7 1884.72  5079.5 1892.72  5101.9 1898.05
  5107.5 1898.65  5124.2 1904.76  5129.8 1905.33  5146.6 1909.29  5174.5 1914.13
  5191.3 1918.44  5196.9 1918.96  5219.3 1924.65  5224.9 1926.86  5227.6 1926.86
#Mann=5,-1,0
  4823.8     0.1       0  4940.6    0.07       0  4973.5    0.05       0
  4977.5    0.07       0  4988.9     0.1       0
Bank Sta=4973.5,4977.5
Exp/Cntr=0.3,0.1

Type RM Length L Ch R = 1,1331,464,464,464
BEGIN DESCRIPTION:
Stream0289 3.0
END DESCRIPTION:
XS GIS Cut Line= 3
      1846625.00     13913925.02      1846625.00     13913825.00
      1846424.98     13913624.98
#Sta/Elev= 30
  4900.4 1886.89  4902.9 1886.89  4910.4 1885.24  4920.4 1884.50  4930.4 1882.30
  4940.4 1879.46  4950.4 1880.19  4960.4 1878.77  4970.4 1873.62  4980.4 1870.64
  4990.4 1868.68  4997.9 1866.62  5004.0 1866.62  5012.5 1865.34  5012.8 1864.84
  5016.4 1864.84  5016.6 1865.34  5023.1 1865.59  5057.0 1867.39  5099.4 1867.13
  5113.6 1871.13  5127.7 1878.39  5141.8 1892.46  5184.3 1910.62  5198.4 1915.98
  5226.7 1924.56  5255.0 1932.12  5269.1 1934.37  5279.7 1937.17  5283.3 1937.17
#Mann=4,-1,0
  4900.4    0.07       0  5012.5    0.05       0  5016.6    0.07       0
  5023.1     0.1       0
Bank Sta=5012.5,5016.6
Exp/Cntr=0.3,0.1

Type RM Length L Ch R = 1,867,392,392,392
BEGIN DESCRIPTION:
Stream0289 2.0
END DESCRIPTION:
XS GIS Cut Line= 3
      1846845.49     13914193.50      1847008.03     13913773.86
      1847025.00     13913625.04
#Sta/Elev= 30
  4535.1 1911.99  4554.9 1909.75  4573.1 1909.85  4578.5 1907.02  4597.7 1905.19
  4613.0 1902.20  4629.8 1900.13  4651.4 1898.33  4694.3 1889.70  4717.1 1886.40
  4758.7 1879.21  4790.9 1875.94  4801.9 1873.32  4821.1 1872.93  4875.6 1867.99
  4925.5 1864.90  4935.4 1864.44  4941.0 1866.19  4951.7 1866.10  4957.9 1864.05
  4958.2 1863.55  4962.1 1864.05  4965.3 1867.59  4981.8 1864.12  5024.2 1865.79
  5034.3 1879.16  5044.4 1888.89  5054.4 1895.71  5090.2 1914.68  5134.9 1926.54
#Mann=8,-1,0
  4535.1    0.07       0  4613.0   0.035       0  4629.8    0.07       0
  4717.1   0.035       0  4925.5    0.07       0  4957.9    0.05       0
  4962.1    0.07       0  5034.3     0.1       0
Bank Sta=4957.9,4962.1
Exp/Cntr=0.3,0.1

Type RM Length L Ch R = 1,475,0,0,0
BEGIN DESCRIPTION:
Stream0289 1.0
END DESCRIPTION:
XS GIS Cut Line= 3
      1847175.01     13914274.97      1847275.00     13914025.00
      1847224.99     13913724.96
#Sta/Elev= 30
  4726.3 1915.89  4747.8 1911.99  4812.4 1895.28  4824.5 1885.73  4843.4 1877.84
  4855.5 1871.41  4866.3 1869.11  4878.4 1864.44  4902.6 1862.17  4910.9 1862.53
  4980.7 1860.15  4992.8 1857.41  4998.1 1857.41  5015.8 1847.01  5026.4 1844.71
  5026.7 1844.21  5030.6 1844.71  5056.4 1846.27  5084.2 1851.22  5089.3 1849.75
  5107.0 1855.86  5112.5 1856.09  5117.2 1856.28  5127.3 1860.03  5150.1 1874.39
  5178.0 1884.94  5205.9 1892.05  5211.0 1892.31  5218.6 1895.22  5299.7 1905.68
#Mann=5,-1,0
  4726.3     0.1       0  4910.9    0.07       0  5026.4    0.05       0
  5030.6    0.07       0  5112.5     0.1       0
Bank Sta=5026.4,5030.6
Exp/Cntr=0.3,0.1

Chan Stop Cuts=-1