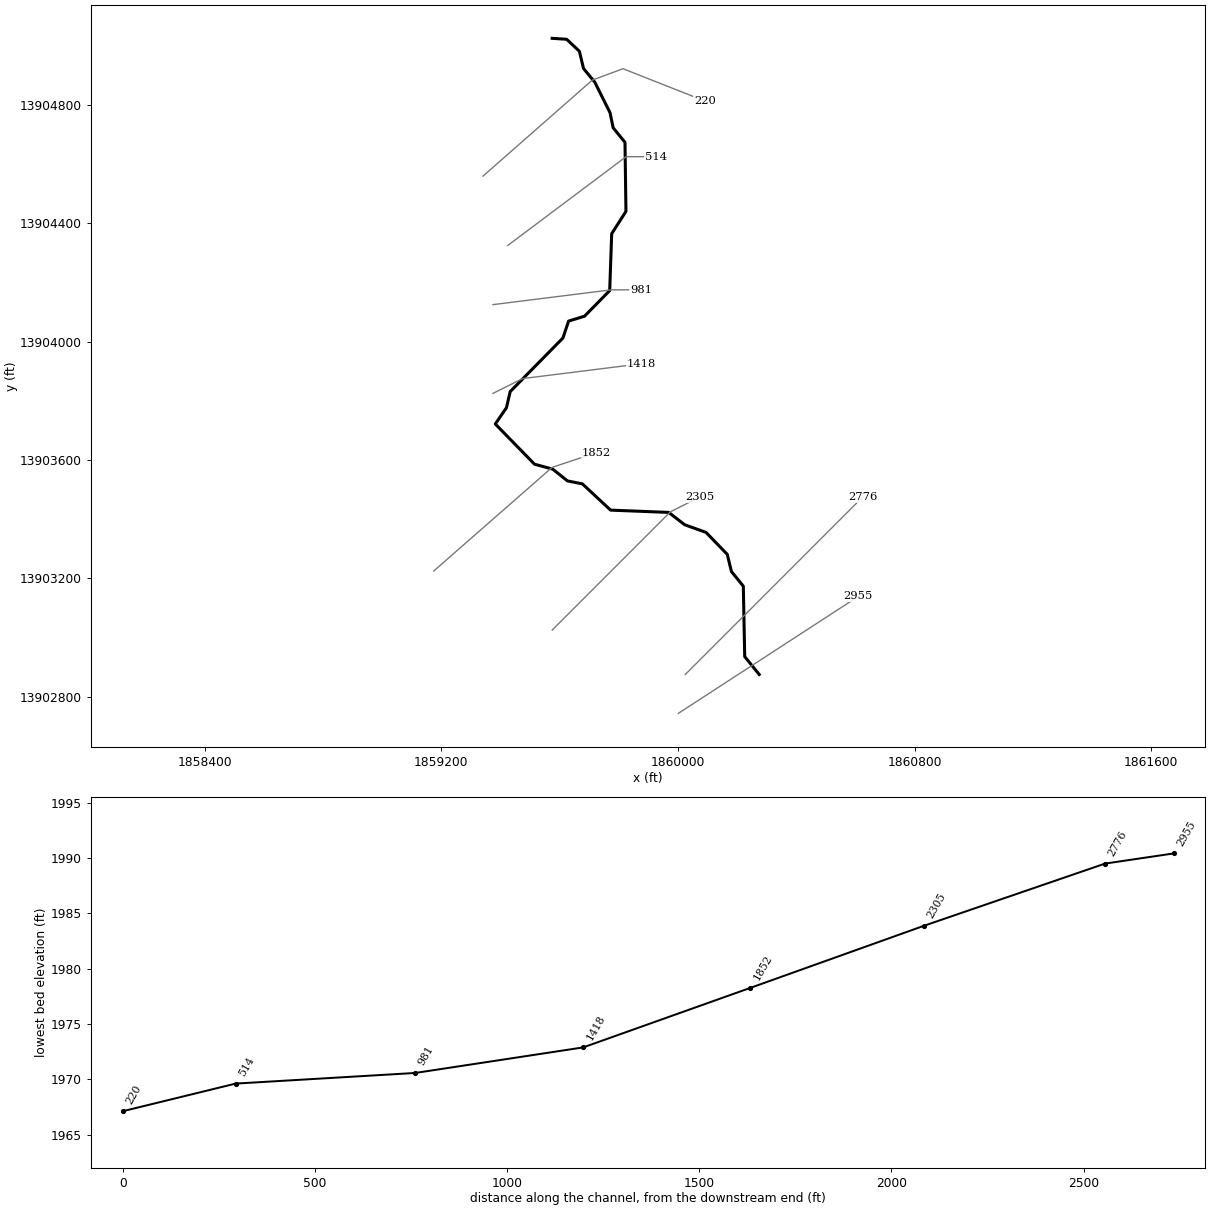
--- Stream0290.prj (project) ---

Proj Title=Stream0290 Base Level Engineering
Current Plan=p01
Default Exp/Contr=0.3,0.1
English Units
Geom File=g01
Flow File=f01
Plan File=p01
Y Axis Title=Elevation
X Axis Title(PF)=Main Channel Distance
X Axis Title(XS)=Station
BEGIN DESCRIPTION:
Stream0290
END DESCRIPTION:
DSS Export Rating Curves= 0
DSS Export Rating Curve Sorted= 0
DSS Export Volume Flow Curves= 0
DXF OffsetX= 0
DXF OffsetY= 0
DXF ScaleX= 1
DXF ScaleY= 10

--- Stream0290.p01 (plan) ---

Plan Title=Multiple Run
Short Identifier=Multiple
Geom File=g01
Flow File=f01
Subcritical Flow
K Sum by GR= 0
Std Step Tol= 0.01
Critical Tol= 0.01
Num of Std Step Trials= 20
Max Error Tol= 0.3
Flow Tol Ratio= 0.001
Split Flow NTrial= 30
Split Flow Tol= 0.02
Split Flow Ratio= 0.02
Log Output Level= 0
Friction Slope Method= 1
Unsteady Friction Slope Method= 2
Unsteady Bridges Friction Slope Method= 1
Parabolic Critical Depth
Global Vel Dist=  1 , 1 , 1
Global Log Level= 0
CheckData=True
Encroach Param= -1, 0, 0, 0
BEGIN DESCRIPTION:
Multiple Run
END DESCRIPTION:

--- Stream0290.f01 (steady flow) ---

Flow Title=Multiple
Number of Profiles=7
Profile Names=10-year,25-year,50-year,1pct_min,100-year,1pct_plu,500-year
River Rch & RM= Stream0290,Reach-1,2955
    2049    3615    5151    3540    7064   14095   13140
Boundary for River Rch & Prof#=Stream0290,Reach-1,1
Up Type=0
Dn Type=3
Dn Slope=0.005
Boundary for River Rch & Prof#=Stream0290,Reach-1,2
Up Type=0
Dn Type=3
Dn Slope=0.005
Boundary for River Rch & Prof#=Stream0290,Reach-1,3
Up Type=0
Dn Type=3
Dn Slope=0.005
Boundary for River Rch & Prof#=Stream0290,Reach-1,4
Up Type=0
Dn Type=3
Dn Slope=0.005
Boundary for River Rch & Prof#=Stream0290,Reach-1,5
Up Type=0
Dn Type=3
Dn Slope=0.005
Boundary for River Rch & Prof#=Stream0290,Reach-1,6
Up Type=0
Dn Type=3
Dn Slope=0.005
Boundary for River Rch & Prof#=Stream0290,Reach-1,7
Up Type=0
Dn Type=3
Dn Slope=0.005

--- Stream0290.g01 (geometry) ---

Geom Title=Existing Conditions
Program Version=4.10

River Reach=Stream0290      ,Reach-1
Reach XY= 30
        1860275.       13902875.      1860225.96      13902935.4
      1860221.25     13903173.45      1860181.14     13903222.83
      1860166.87     13903281.07      1860095.13     13903355.23
      1860022.83     13903381.14      1859969.07     13903422.76
      1859772.55     13903430.47      1859677.29     13903519.15
      1859626.73     13903529.19      1859577.19      13903568.9
      1859515.32     13903585.76      1859382.77     13903721.59
      1859420.53     13903776.65      1859433.12     13903831.05
      1859611.27     13904012.02      1859630.62     13904069.38
      1859684.44     13904085.88      1859769.54     13904172.53
      1859776.22     13904364.49      1859824.48     13904440.22
      1859821.25     13904673.45      1859781.12     13904722.82
      1859770.84     13904773.28      1859718.92      13904877.2
      1859681.09     13904922.82      1859667.04     13904981.31
      1859623.97     13905021.86        1859575.       13905025.

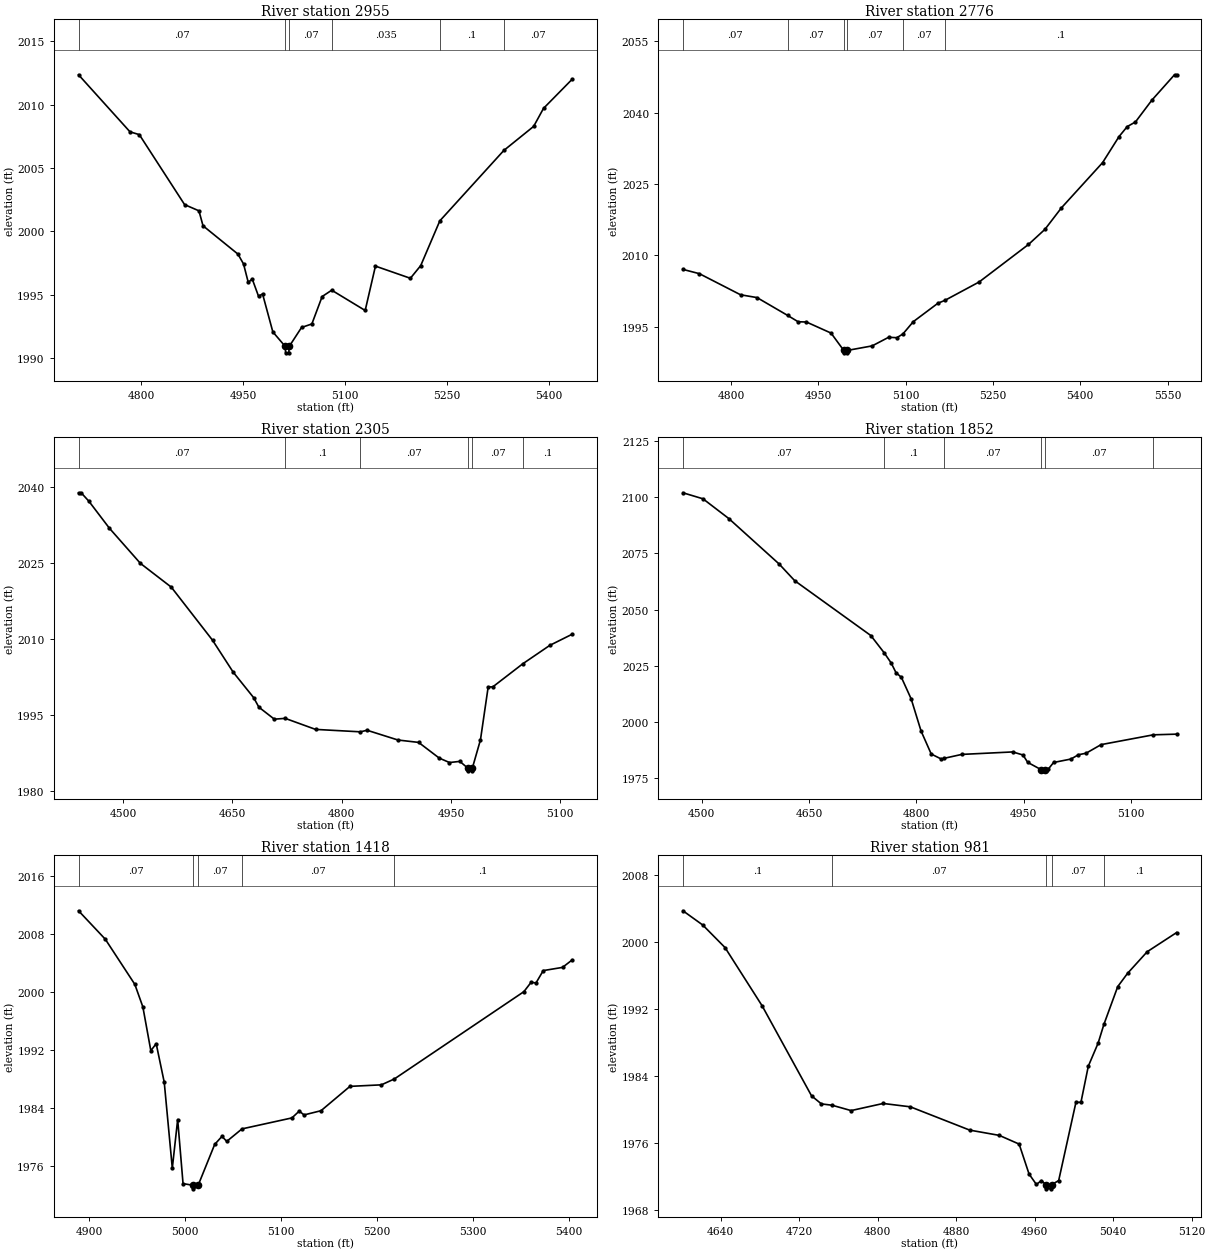
Type RM Length L Ch R = 1 ,2955    ,179,179,179
BEGIN DESCRIPTION:
Stream0290 7.0
END DESCRIPTION:
XS GIS Cut Line= 2
      1860001.49     13902743.55       1860610.4     13903139.08
#Sta/Elev= 30
  4708.1 2012.36  4783.8 2007.86  4797.5 2007.64  4864.1 2002.12  4885.2 2001.63
  4891.2 2000.45  4942.5 1998.22  4950.8 1997.44  4957.7 1995.99  4963.6 1996.25
  4972.8  1994.9  4978.8 1995.07  4993.9 1992.08  5012.2 1990.93  5012.6 1990.43
  5017.4 1990.43  5017.9 1990.93  5036.1 1992.43  5051.3 1992.71  5066.4 1994.87
  5080.5 1995.37  5129.7 1993.77  5144.8 1997.27  5196.2 1996.31  5211.4 1997.31
  5239.5 2000.84  5333.6 2006.39  5377.5 2008.29    5392 2009.71  5434.2 2012.01
#Mann= 6 ,-1 , 0
  4708.1     .07       0  5012.2     .05       0  5017.9     .07       0
  5080.5    .035       0  5239.5      .1       0  5333.6     .07       0
Bank Sta=5012.2,5017.9
XS Rating Curve= 0 ,0
Exp/Cntr=0.3,0.1

Type RM Length L Ch R = 1 ,2776    ,471,471,471
BEGIN DESCRIPTION:
Stream0290 6.0
END DESCRIPTION:
XS GIS Cut Line= 3
      1860024.97     13902874.97        1860225.       13903075.
      1860625.02     13903475.02
#Sta/Elev= 30
    4717 2007.04  4745.3 2006.14    4816 2001.71  4844.3 2001.12    4897 1997.37
    4915 1996.04  4929.2 1995.99  4971.6 1993.66  4993.5 1990.01  4993.9 1989.51
  4998.7 1989.51  4999.2 1990.01  5042.3 1990.97  5070.6 1992.78  5084.7 1992.69
  5095.1 1993.47    5113 1996.06  5155.4 1999.94  5167.1 2000.52  5226.2  2004.4
    5311 2012.28  5339.3 2015.46  5367.6 2019.97  5438.3 2029.46  5466.6 2034.94
  5480.7 2037.04  5494.9 2038.02  5523.1  2042.6    5562 2047.93  5565.6 2047.93
#Mann= 6 ,-1 , 0
    4717     .07       0    4897     .07       0  4993.5     .05       0
  4999.2     .07       0  5095.1     .07       0  5167.1      .1       0
Bank Sta=4993.5,4999.2
XS Rating Curve= 0 ,0
Exp/Cntr=0.3,0.1

Type RM Length L Ch R = 1 ,2305    ,453,453,453
BEGIN DESCRIPTION:
Stream0290 5.0
END DESCRIPTION:
XS GIS Cut Line= 3
      1859574.99     13903024.99        1859975.       13903425.
      1860074.99       13903475.
#Sta/Elev= 30
  4438.8 2038.84  4442.4 2038.84    4453 2037.17  4481.2 2031.83  4523.7 2024.89
  4566.1 2020.19  4622.7  2009.7    4651  2003.4  4679.2 1998.34  4686.3 1996.47
  4707.5  1994.1  4722.4 1994.26  4764.1 1992.08  4825.6  1991.6  4834.8 1991.91
  4877.2 1989.98  4905.5 1989.51  4933.8 1986.41  4947.9 1985.53  4962.1 1985.76
  4973.3 1984.39  4973.8 1983.89  4978.7 1983.89  4979.2 1984.39  4990.4 1990.02
    5001 2000.48  5007.3 2000.48  5048.6 2005.06  5085.6 2008.69  5116.3 2010.89
#Mann= 6 ,-1 , 0
  4438.8     .07       0  4722.4      .1       0  4825.6     .07       0
  4973.3     .05       0  4979.2     .07       0  5048.6      .1       0
Bank Sta=4973.3,4979.2
XS Rating Curve= 0 ,0
Exp/Cntr=0.3,0.1

Type RM Length L Ch R = 1 ,1852    ,434,434,434
BEGIN DESCRIPTION:
Stream0290 4.0
END DESCRIPTION:
XS GIS Cut Line= 3
      1859174.98     13903224.98        1859575.       13903575.
      1859725.05     13903625.02
#Sta/Elev= 30
  4473.7 2101.94  4501.7 2099.26  4537.8 2090.47    4608 2070.29  4629.9 2062.82
  4736.2 2038.44  4754.6 2030.87  4764.6 2026.25  4771.3 2021.96  4778.9 2019.84
  4792.6 2010.23  4806.4 1995.96  4820.6 1985.74  4834.9 1983.47  4838.2  1983.8
  4863.3 1985.57  4934.5 1986.67  4948.8  1985.3  4955.4 1982.02  4974.3 1978.76
  4974.8 1978.26  4980.2 1978.76  4983.9 1978.93  4991.5 1981.97  5015.8 1983.51
  5026.3 1985.43  5036.9 1986.09  5057.9 1989.92  5130.9 1994.28  5163.4 1994.58
#Mann= 6 ,-1 , 0
  4473.7     .07       0  4754.6      .1       0  4838.2     .07       0
  4974.3     .05       0  4980.2     .07       0  5130.9      .1       0
Bank Sta=4974.3,4980.2
XS Rating Curve= 0 ,0
Exp/Cntr=0.3,0.1

Type RM Length L Ch R = 1 ,1418    ,437,437,437
BEGIN DESCRIPTION:
Stream0290 3.0
END DESCRIPTION:
XS GIS Cut Line= 3
      1859375.02     13903825.01        1859475.       13903875.
        1859875.       13903925.
#Sta/Elev= 30
  4888.9 2011.15  4916.8 2007.24  4947.6 2001.03    4956 1997.92  4964.3  1991.9
  4969.9 1992.86  4978.3 1987.55  4986.7 1975.73  4992.3 1982.43  4997.9 1973.61
  5007.8 1973.39  5008.3 1972.89  5013.7 1973.39  5030.9    1979  5038.5 1980.11
  5043.5 1979.42  5059.4 1981.14  5111.5 1982.65  5119.1 1983.59  5124.1 1983.06
  5141.8 1983.64    5172 1986.99  5204.8  1987.2  5218.3 1988.01  5353.4 2000.02
    5361 2001.32    5366 2001.21  5373.6 2002.92  5393.7 2003.36  5403.8 2004.39
#Mann= 5 ,-1 , 0
  4888.9     .07       0  5007.8     .05       0  5013.7     .07       0
  5059.4     .07       0  5218.3      .1       0
Bank Sta=5007.8,5013.7
XS Rating Curve= 0 ,0
Exp/Cntr=0.3,0.1

Type RM Length L Ch R = 1 ,981     ,467,467,467
BEGIN DESCRIPTION:
Stream0290 2.0
END DESCRIPTION:
XS GIS Cut Line= 3
      1859374.95     13904124.99        1859775.       13904175.
      1859875.04       13904175.
#Sta/Elev= 30
  4601.4 2003.77  4621.6 2002.07  4644.3 1999.38  4682.1 1992.43  4732.5 1981.68
  4742.5 1980.72  4753.4 1980.56  4772.8 1979.92  4805.5 1980.77  4833.2 1980.37
  4893.7 1977.59  4923.9 1976.96  4944.1 1975.92  4954.2 1972.35  4961.7  1971.1
  4966.8 1971.57  4971.3 1971.08  4971.8 1970.58  4976.8 1970.58  4977.3 1971.08
  4984.4 1971.57    5002 1980.91  5007.1 1980.91  5014.6 1985.22  5024.6 1987.97
  5030.5 1990.21  5044.6 1994.72  5054.6  1996.3  5074.6 1998.88  5104.6 2001.17
#Mann= 5 ,-1 , 0
  4601.4      .1       0  4753.4     .07       0  4971.3     .05       0
  4977.3     .07       0  5030.5      .1       0
Bank Sta=4971.3,4977.3
XS Rating Curve= 0 ,0
Exp/Cntr=0.3,0.1

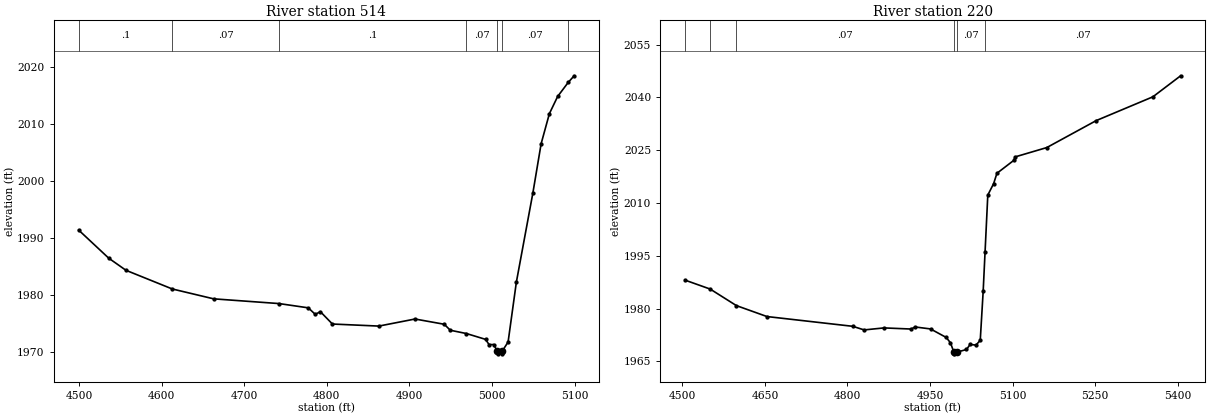
Type RM Length L Ch R = 1 ,514     ,294,294,294
BEGIN DESCRIPTION:
Stream0290 1.0
END DESCRIPTION:
XS GIS Cut Line= 3
        1859425.       13904325.        1859825.       13904625.
      1859925.01       13904625.
#Sta/Elev= 30
  4499.6 1991.34  4536.1  1986.4  4556.9 1984.28    4613    1981  4663.1 1979.27
  4742.3 1978.44  4777.7 1977.69  4786.1 1976.55  4792.3 1977.02  4806.9 1974.85
  4863.1 1974.49  4906.9 1975.73  4942.3 1974.81  4949.6 1973.76  4969.2 1973.18
  4992.3 1972.16  4996.5 1971.25  5002.1 1971.25  5006.5 1970.12    5007 1969.62
  5012.1 1969.62  5012.6 1970.12  5019.6  1971.7  5029.6  1982.2  5049.6 1997.85
  5059.6 2006.49  5069.6 2011.77  5079.6 2014.78  5092.4 2017.25  5099.6 2018.41
#Mann= 7 ,-1 , 0
  4499.6      .1       0    4613     .07       0  4742.3      .1       0
  4969.2     .07       0  5006.5     .05       0  5012.6     .07       0
  5092.4      .1       0
Bank Sta=5006.5,5012.6
XS Rating Curve= 0 ,0
Exp/Cntr=0.3,0.1

Type RM Length L Ch R = 1 ,220     ,0,0,0
BEGIN DESCRIPTION:
Stream0290 0.0
END DESCRIPTION:
XS GIS Cut Line= 4
      1859341.19     13904559.33      1859710.53     13904883.66
      1859814.36     13904922.34       1860091.2     13904813.23
#Sta/Elev= 30
  4505.1 1988.07  4550.7 1985.53  4598.3 1980.83  4653.8 1977.72  4809.4 1974.95
  4830.3 1973.92  4866.3 1974.49  4915.7 1974.17  4922.7 1974.76  4950.8  1974.2
  4979.3 1971.78  4986.9 1970.28  4993.2 1967.62  4993.7 1967.12  4999.3 1967.62
  5016.1 1968.36  5022.7 1969.79  5033.4 1969.61  5041.1 1970.97  5046.4  1984.9
  5049.8 1995.97  5054.8 2012.25  5065.4 2015.51  5071.4 2018.45  5101.8  2022.1
  5105.1 2023.14  5161.9 2025.76  5251.7 2033.43  5354.6 2040.19    5405 2046.17
#Mann= 6 ,-1 , 0
  4505.1      .1       0  4550.7     .07       0  4598.3     .07       0
  4993.2     .05       0  4999.3     .07       0  5049.8     .07       0
Bank Sta=4993.2,4999.3
XS Rating Curve= 0 ,0
Exp/Cntr=0.3,0.1

Chan Stop Cuts=-1
Use User Specified Reach Order=0
Composite Channel Slope=5