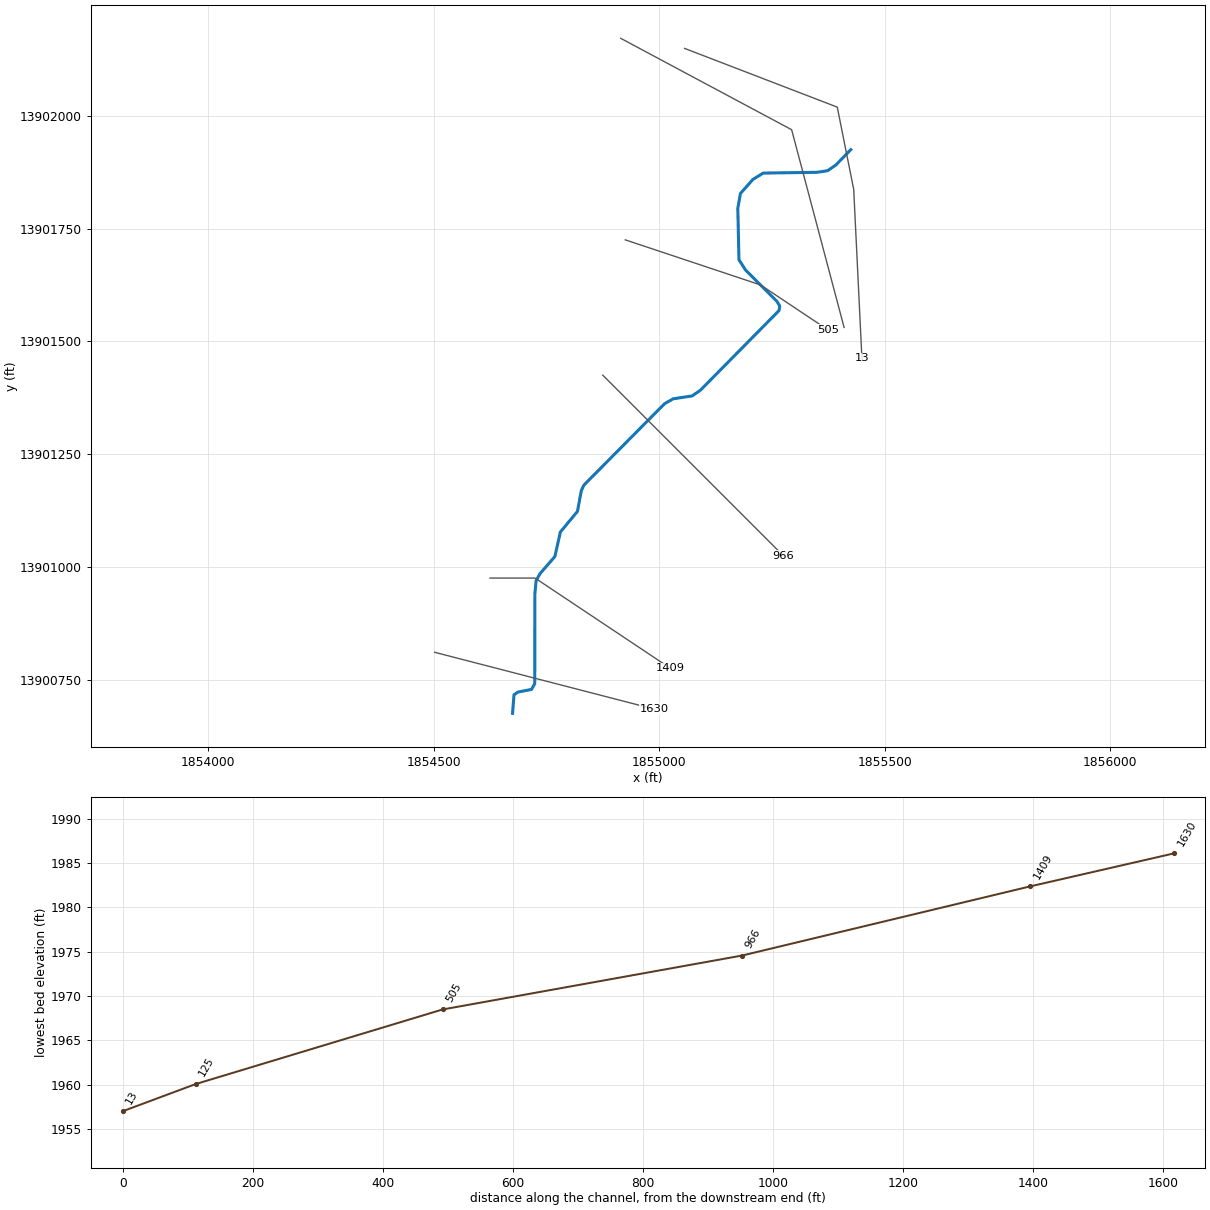
--- Stream0294.prj (project) ---

Proj Title=Stream0294 Base Level Engineering
Current Plan=p01
Default Exp/Contr=0.3,0.1
English Units
Geom File=g01
Flow File=f01
Plan File=p01
Y Axis Title=Elevation
X Axis Title(PF)=Main Channel Distance
X Axis Title(XS)=Station
BEGIN DESCRIPTION:
Stream0294
END DESCRIPTION:
DSS Export Rating Curves= 0
DSS Export Rating Curve Sorted= 0
DSS Export Volume Flow Curves= 0
DXF OffsetX= 0
DXF OffsetY= 0
DXF ScaleX= 1
DXF ScaleY= 10

--- Stream0294.p01 (plan) ---

Plan Title=Multiple Run
Short Identifier=Multiple
Geom File=g01
Flow File=f01
Subcritical Flow
K Sum by GR= 0
Std Step Tol= 0.01
Critical Tol= 0.01
Num of Std Step Trials= 20
Max Error Tol= 0.3
Flow Tol Ratio= 0.001
Split Flow NTrial= 30
Split Flow Tol= 0.02
Split Flow Ratio= 0.02
Log Output Level= 0
Friction Slope Method= 1
Unsteady Friction Slope Method= 2
Unsteady Bridges Friction Slope Method= 1
Parabolic Critical Depth
Global Vel Dist=  1 , 1 , 1
Global Log Level= 0
CheckData=True
Encroach Param= -1, 0, 0, 0
BEGIN DESCRIPTION:
Multiple Run
END DESCRIPTION:

--- Stream0294.f01 (steady flow) ---

Flow Title=Multiple
Program Version=4.10
Number of Profiles= 7
Profile Names=10-year,25-year,50-year,1pct_min,100-year,1pct_plu,500-year
River Rch & RM=Stream0294,Reach-1         ,1630
    1194    2067    2912    1985    3960    7901    7235
Boundary for River Rch & Prof#=Stream0294,Reach-1         , 1
Up Type= 0
Dn Type= 3
Dn Slope=0.005
Boundary for River Rch & Prof#=Stream0294,Reach-1         , 2
Up Type= 0
Dn Type= 3
Dn Slope=0.005
Boundary for River Rch & Prof#=Stream0294,Reach-1         , 3
Up Type= 0
Dn Type= 3
Dn Slope=0.005
Boundary for River Rch & Prof#=Stream0294,Reach-1         , 4
Up Type= 0
Dn Type= 3
Dn Slope=0.005
Boundary for River Rch & Prof#=Stream0294,Reach-1         , 5
Up Type= 0
Dn Type= 3
Dn Slope=0.005
Boundary for River Rch & Prof#=Stream0294,Reach-1         , 6
Up Type= 0
Dn Type= 3
Dn Slope=0.005
Boundary for River Rch & Prof#=Stream0294,Reach-1         , 7
Up Type= 0
Dn Type= 3
Dn Slope=0.005
DSS Import GetInterval= 0
DSS Import GetPeak= 0
DSS Import FillOption= 0

--- Stream0294.g01 (geometry) ---

Geom Title=Existing Conditions
Program Version=4.10

River Reach=Stream0294      ,Reach-1
Reach XY= 30
        1854675.       13900675.      1854678.24     13900716.31
      1854687.55     13900722.45      1854716.93     13900728.07
      1854724.24     13900740.76      1854724.56     13900940.18
      1854727.24     13900969.07       1854735.8     13900984.67
      1854768.88     13901022.82      1854781.08      13901077.2
       1854818.9     13901122.81       1854827.5     13901168.97
      1854833.14     13901181.06      1855011.79     13901361.37
      1855031.05     13901372.47      1855073.35     13901378.98
      1855091.67     13901391.65      1855266.04     13901568.33
       1855267.4     13901578.33      1855261.56     13901588.32
       1855191.5     13901658.24      1855177.06     13901680.86
       1855174.5     13901795.24      1855180.33     13901827.74
      1855207.77     13901858.76      1855230.65     13901873.02
      1855350.09     13901874.79      1855373.63      13901878.3
      1855392.06     13901891.09        1855425.       13901925.

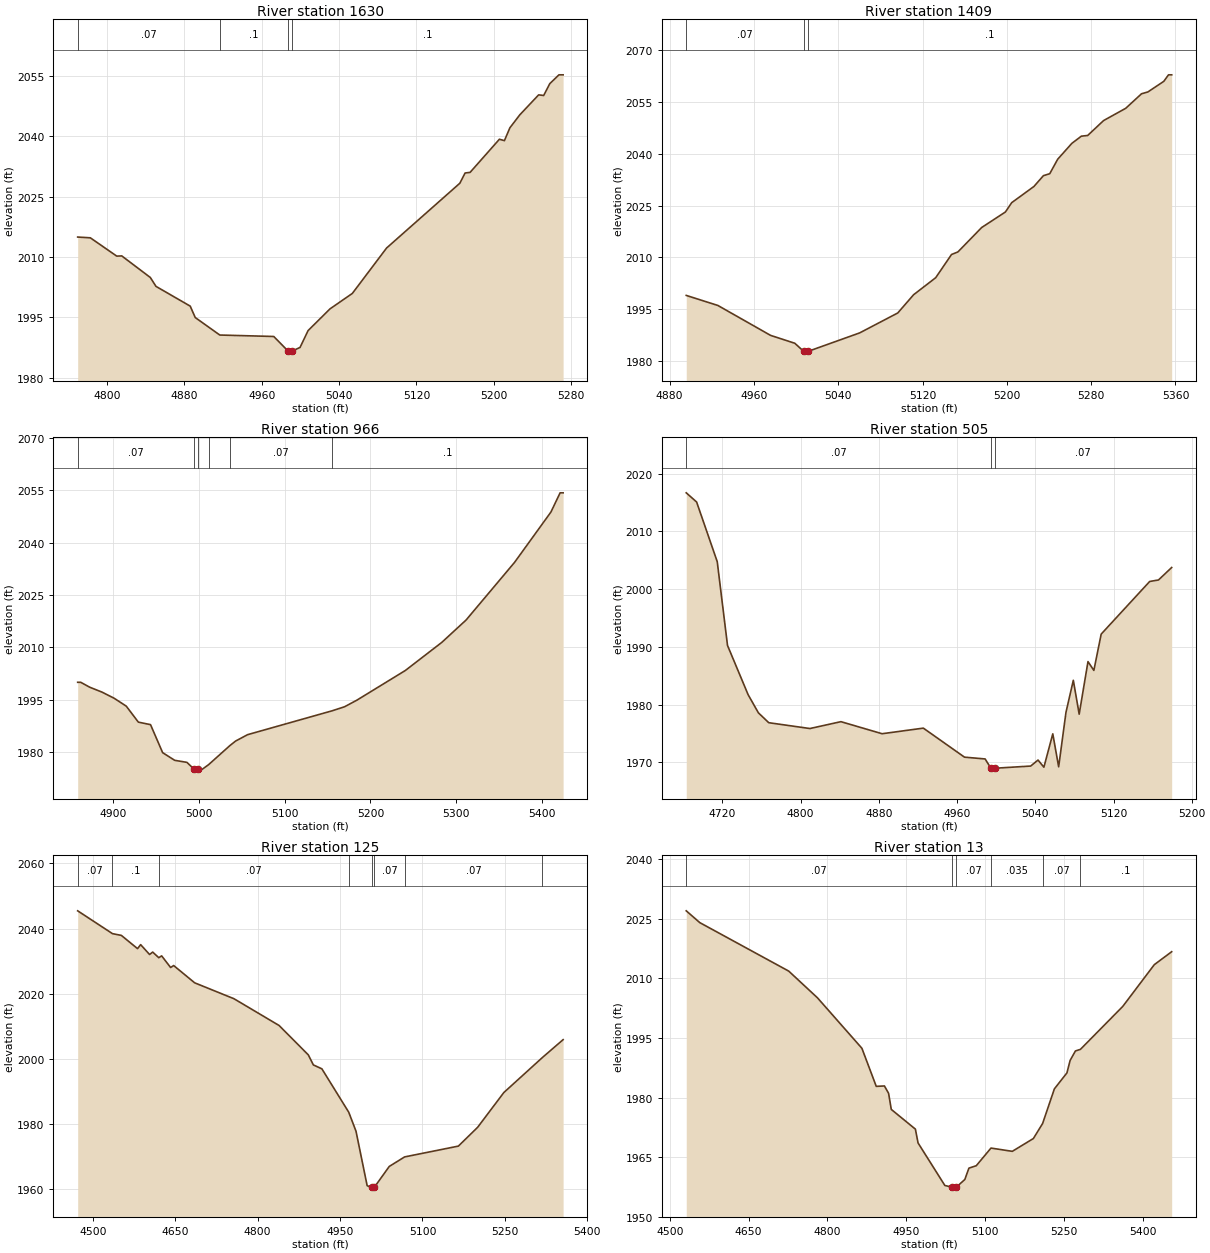
Type RM Length L Ch R = 1 ,1630    ,221,221,221
BEGIN DESCRIPTION:
Stream0294 4.0
END DESCRIPTION:
XS GIS Cut Line= 2
      1854502.29     13900810.48      1854988.38     13900684.67
#Sta/Elev= 30
  4769.6 2014.95  4782.7 2014.76    4810 2010.21  4815.2 2010.26  4844.7  2004.9
  4850.6 2002.68    4886 1997.77  4891.2 1994.93  4916.6 1990.58  4972.4 1990.22
  4987.3 1986.58  4987.6 1986.08  4991.3 1986.58  4999.6  1987.5  5007.9 1991.68
  5030.6 1997.09  5053.7 2000.93  5089.1 2012.22  5164.9 2028.34  5170.3 2030.88
  5175.5 2031.04  5205.8 2039.28    5211 2038.93  5216.6 2042.11  5226.9 2045.35
  5246.4 2050.32  5251.6 2050.16  5257.9  2053.1  5267.4  2055.3  5271.7  2055.3
#Mann= 4 ,-1 , 0
  4769.6     .07       0  4916.6      .1       0  4987.3     .05       0
  4991.3      .1       0
Bank Sta=4987.3,4991.3
XS Rating Curve= 0 ,0
Exp/Cntr=0.3,0.1

Type RM Length L Ch R = 1 ,1409    ,443,443,443
BEGIN DESCRIPTION:
Stream0294 3.0
END DESCRIPTION:
XS GIS Cut Line= 3
      1854624.99       13900975.        1854725.       13900975.
      1855025.03     13900774.98
#Sta/Elev= 30
  4895.8 1999.03  4925.8 1996.13  4975.8 1987.49  4998.8 1985.21  5007.3 1982.86
  5007.6 1982.36  5011.3 1982.86  5060.4 1988.21  5096.5 1993.96  5111.5 1999.22
  5132.5 2004.15  5147.5 2010.85  5153.6  2011.6  5176.1 2018.64  5198.6 2023.12
  5204.6 2025.82  5225.7  2030.5  5234.7 2033.62  5240.7 2034.19  5248.2 2038.35
  5261.7 2042.96  5270.7 2045.03  5276.7 2045.23  5291.8 2049.54  5312.8 2053.08
  5327.8 2057.28  5333.8  2057.8  5348.9 2060.86  5353.4 2062.75  5356.4 2062.75
#Mann= 3 ,-1 , 0
  4895.8     .07       0  5007.3     .05       0  5011.3      .1       0
Bank Sta=5007.3,5011.3
XS Rating Curve= 0 ,0
Exp/Cntr=0.3,0.1

Type RM Length L Ch R = 1 ,966     ,461,461,461
BEGIN DESCRIPTION:
Stream0294 2.0
END DESCRIPTION:
XS GIS Cut Line= 3
        1854875.       13901425.        1854975.       13901325.
      1855275.01     13901024.99
#Sta/Elev= 30
  4858.8    2000  4862.3    2000  4872.9 1998.58  4887.1 1997.19  4901.2 1995.44
  4915.4 1993.17  4929.5 1988.59  4943.7 1987.87  4957.8 1979.85  4971.9 1977.65
  4986.1 1977.07  4994.7 1975.06  4994.9 1974.56  4998.4 1974.56  4998.7 1975.06
  5003.8 1975.06  5011.4 1976.42  5036.1 1981.86  5042.7 1983.15  5056.8    1985
  5155.4 1991.84  5169.9    1993  5184.1 1994.87  5240.6 2003.37  5283.1 2011.42
  5311.4 2017.82  5367.9 2034.33  5410.3 2048.75    5421 2054.25  5424.5 2054.25
#Mann= 6 ,-1 , 0
  4858.8     .07       0  4994.7     .05       0  4998.7     .07       0
  5011.4    .035       0  5036.1     .07       0  5155.4      .1       0
Bank Sta=4994.7,4998.7
XS Rating Curve= 0 ,0
Exp/Cntr=0.3,0.1

Type RM Length L Ch R = 1 ,505     ,380,380,380
BEGIN DESCRIPTION:
Stream0294 1.0
END DESCRIPTION:
XS GIS Cut Line= 3
      1854924.96     13901725.01        1855225.       13901625.
      1855374.96     13901525.03
#Sta/Elev= 30
    4683 2016.69  4693.6  2015.1  4714.7 2004.76  4725.2 1990.25  4746.3 1981.71
  4756.8 1978.57  4767.4 1976.86  4809.5 1975.85  4841.2 1977.04  4883.3 1974.95
  4925.5 1975.92  4967.6 1970.89  4988.7 1970.58  4994.6 1968.97  4994.9 1968.47
  4998.6 1968.97  5035.3 1969.35  5042.8 1970.39  5048.8 1969.15  5057.9 1974.93
  5063.9 1969.22  5071.4 1978.67  5078.9 1984.21  5084.9 1978.34  5093.9 1987.45
  5099.9 1985.92  5107.4 1992.21    5157 2001.33    5166 2001.59  5179.5 2003.75
#Mann= 3 ,-1 , 0
    4683     .07       0  4994.6     .05       0  4998.6     .07       0
Bank Sta=4994.6,4998.6
XS Rating Curve= 0 ,0
Exp/Cntr=0.3,0.1

Type RM Length L Ch R = 1 ,125     ,112,112,112
BEGIN DESCRIPTION:
Stream0294 0.0
END DESCRIPTION:
XS GIS Cut Line= 3
      1854914.92     13902171.85      1855293.88     13901969.22
      1855410.21     13901530.72
#Sta/Elev= 30
  4472.6 2045.44  4535.9 2038.44  4552.1  2037.9  4581.5 2033.84  4587.2 2035.06
  4603.4 2032.04  4609.1 2032.78  4620.2 2031.06  4625.4 2031.62  4641.7 2028.05
  4647.3 2028.65  4685.5 2023.35    4757 2018.47  4839.1 2010.26  4892.3 2001.24
  4901.5 1998.16    4917 1996.96  4965.9 1983.64  4979.1 1977.82  4999.4  1961.1
  5008.2 1960.55  5008.4 1960.05  5012.2 1960.55  5039.6 1967.01  5067.5 1969.93
  5165.4 1973.25  5200.4 1979.01  5248.1 1989.68  5318.3 2000.43    5356 2005.91
#Mann= 8 ,-1 , 0
  4472.6     .07       0  4535.9      .1       0  4620.2     .07       0
  4965.9     .07       0  5008.2     .05       0  5012.2     .07       0
  5067.5     .07       0  5318.3      .1       0
Bank Sta=5008.2,5012.2
XS Rating Curve= 0 ,0
Exp/Cntr=0.3,0.1

Type RM Length L Ch R = 1 ,13      ,0,0,0
BEGIN DESCRIPTION:
Stream0294 0.1
END DESCRIPTION:
XS GIS Cut Line= 4
      1855056.52     13902149.52      1855395.05     13902019.31
      1855431.51     13901837.02      1855449.74     13901461.97
#Sta/Elev= 30
  4531.3 2027.02  4557.1 2024.05  4726.4 2011.85  4781.1 2005.13  4865.7 1992.43
    4893 1982.85  4908.6 1982.95  4916.5 1981.09  4921.6 1977.05  4967.5 1972.09
  4972.6 1968.61  5023.6 1957.91    5037 1957.49  5037.5 1956.99  5045.4 1957.49
  5061.6 1959.41  5069.4 1962.27  5083.4 1962.88  5111.4 1967.32    5152  1966.5
  5192.1 1969.72  5209.7  1973.5  5232.1 1982.22    5256 1986.24  5262.1 1989.39
  5272.2 1991.76  5281.7 1992.16  5362.3 2002.97  5422.3 2013.47  5455.4 2016.73
#Mann= 6 ,-1 , 0
  4531.3     .07       0    5037     .05       0  5045.4     .07       0
  5111.4    .035       0  5209.7     .07       0  5281.7      .1       0
Bank Sta=5037,5045.4
XS Rating Curve= 0 ,0
Exp/Cntr=0.3,0.1

Chan Stop Cuts=-1
Use User Specified Reach Order=0
Composite Channel Slope=5