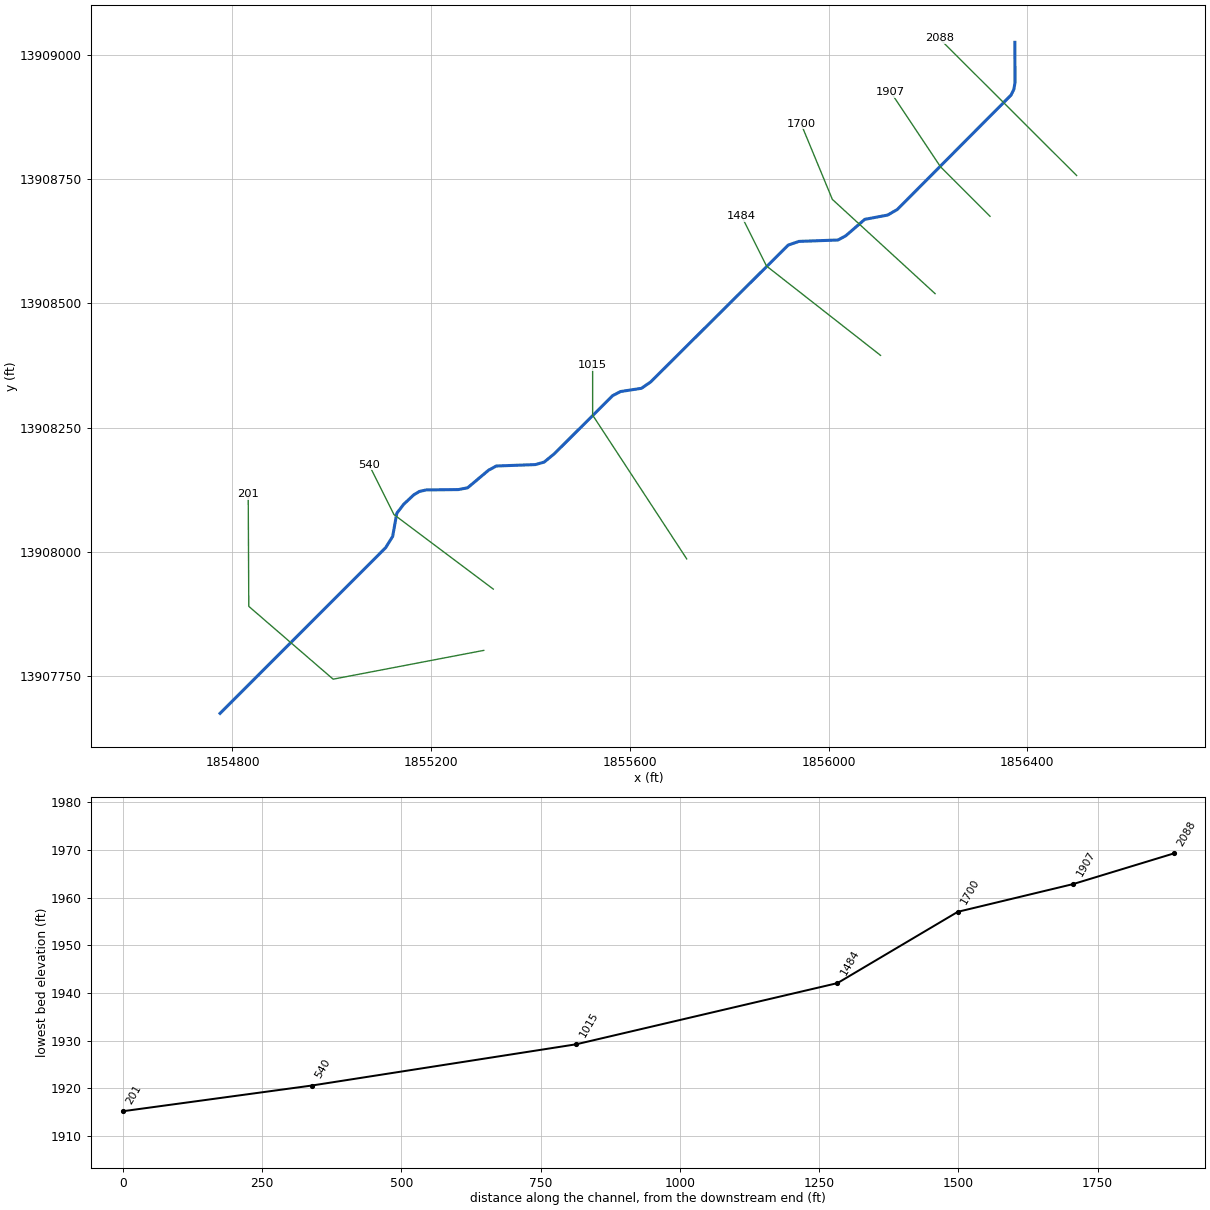
--- Stream0296.prj (project) ---

Proj Title=Stream0296 Base Level Engineering
Current Plan=p01
Default Exp/Contr=0.3,0.1
English Units
Geom File=g01
Flow File=f01
Plan File=p01
BEGIN DESCRIPTION:
Stream0296
END DESCRIPTION:

--- Stream0296.p01 (plan) ---

Plan Title=Multiple Run
Short Identifier=Multiple
Geom File=g01
Flow File=f01
Subcritical Flow
K Sum by GR= 0
Std Step Tol= 0.01
Critical Tol= 0.01
Num of Std Step Trials= 20
Max Error Tol= 0.3
Flow Tol Ratio= 0.001
Split Flow NTrial= 30
Split Flow Tol= 0.02
Split Flow Ratio= 0.02
Log Output Level= 0
Friction Slope Method= 1
Unsteady Friction Slope Method= 2
Unsteady Bridges Friction Slope Method= 1
Parabolic Critical Depth
Global Vel Dist=  1 , 1 , 1
Global Log Level= 0
CheckData=True
Encroach Param= -1, 0, 0, 0
BEGIN DESCRIPTION:
Multiple Run
END DESCRIPTION:

--- Stream0296.f01 (steady flow) ---

Flow Title=Multiple
Number of Profiles=7
Profile Names=10-year,25-year,50-year,1pct_min,100-year,1pct_plu,500-year
River Rch & RM= Stream0296,Reach-1,2088
     617    1024    1403     934    1863    3716    3233
Boundary for River Rch & Prof#=Stream0296,Reach-1,1
Up Type=0
Dn Type=3
Dn Slope=0.005
Boundary for River Rch & Prof#=Stream0296,Reach-1,2
Up Type=0
Dn Type=3
Dn Slope=0.005
Boundary for River Rch & Prof#=Stream0296,Reach-1,3
Up Type=0
Dn Type=3
Dn Slope=0.005
Boundary for River Rch & Prof#=Stream0296,Reach-1,4
Up Type=0
Dn Type=3
Dn Slope=0.005
Boundary for River Rch & Prof#=Stream0296,Reach-1,5
Up Type=0
Dn Type=3
Dn Slope=0.005
Boundary for River Rch & Prof#=Stream0296,Reach-1,6
Up Type=0
Dn Type=3
Dn Slope=0.005
Boundary for River Rch & Prof#=Stream0296,Reach-1,7
Up Type=0
Dn Type=3
Dn Slope=0.005

--- Stream0296.g01 (geometry) ---

Geom Title=Existing Conditions

River Reach=Stream0296,Reach-1
Reach XY= 30
      1856375.00     13909025.00      1856375.33     13908944.86
      1856373.14     13908930.77      1856367.26     13908918.78
      1856138.22     13908688.62      1856118.97     13908677.50
      1856072.83     13908668.86      1856034.65     13908635.84
      1856019.03     13908627.33      1855940.22     13908624.48
      1855918.83     13908617.14      1855641.67     13908341.65
      1855623.35     13908328.98      1855581.05     13908322.46
      1855565.32     13908314.22      1855448.52     13908197.88
      1855427.43     13908180.52      1855409.78     13908175.52
      1855330.98     13908172.64      1855315.37     13908164.11
      1855273.40     13908128.86      1855254.89     13908125.25
      1855190.09     13908124.53      1855176.28     13908121.48
      1855164.90     13908114.61      1855144.59     13908095.57
      1855130.74     13908077.57      1855122.45     13908031.09
      1855108.34     13908008.34      1854775.00     13907675.00

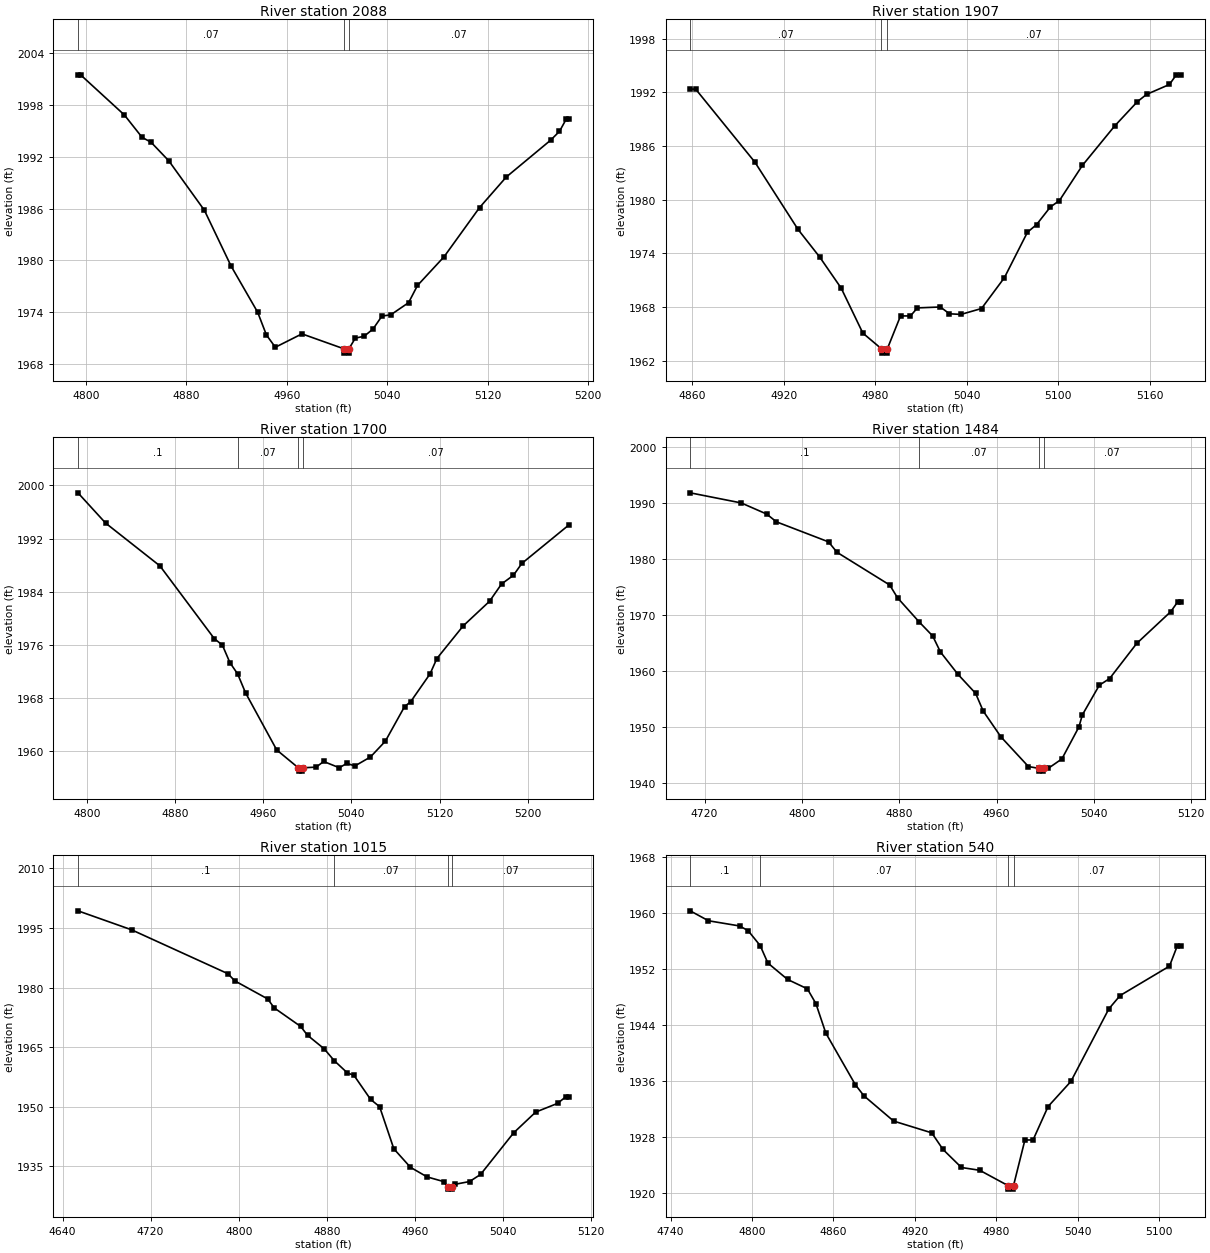
Type RM Length L Ch R = 1,2088,181,181,181
BEGIN DESCRIPTION:
Stream0296 5.0
END DESCRIPTION:
XS GIS Cut Line= 2
      1856499.35     13908757.02      1856222.69     13909033.03
#Sta/Elev= 30
  4793.7 2001.48  4795.8 2001.48  4830.7 1996.83  4844.8 1994.24  4851.9 1993.68
  4866.1 1991.52  4894.4 1985.80  4915.6 1979.36  4936.8 1974.01  4943.8 1971.37
  4950.9 1969.95  4972.1 1971.50  5005.5 1969.77  5005.7 1969.27  5009.2 1969.27
  5009.5 1969.77  5014.6 1971.01  5021.6 1971.22  5028.7 1972.06  5035.8 1973.56
  5042.8 1973.70  5057.0 1975.11  5064.1 1977.10  5085.3 1980.43  5113.5 1986.11
  5134.8 1989.65  5170.1 1993.91  5177.2 1994.94  5182.4 1996.31  5184.5 1996.31
#Mann=3,-1,0
  4793.7    0.07       0  5005.5    0.05       0  5009.5    0.07       0
Bank Sta=5005.5,5009.5
Exp/Cntr=0.3,0.1

Type RM Length L Ch R = 1,1907,207,207,207
BEGIN DESCRIPTION:
Stream0296 4.0
END DESCRIPTION:
XS GIS Cut Line= 3
      1856325.01     13908674.99      1856225.00     13908775.00
      1856125.01     13908924.98
#Sta/Elev= 30
  4858.6 1992.36  4862.2 1992.36  4901.0 1984.20  4929.3 1976.67  4943.5 1973.58
  4957.6 1970.10  4971.8 1965.07  4983.9 1963.33  4984.1 1962.83  4987.6 1962.83
  4987.9 1963.33  4996.5 1966.99  5003.0 1966.99  5007.6 1967.89  5022.6 1967.99
  5028.6 1967.23  5036.1 1967.16  5049.6 1967.82  5064.6 1971.27  5079.7 1976.35
  5085.7 1977.21  5094.7 1979.17  5100.7 1979.90  5115.7 1983.82  5136.8 1988.22
  5151.8 1990.96  5157.8 1991.77  5172.8 1992.88  5177.3 1993.96  5180.3 1993.96
#Mann=3,-1,0
  4858.6    0.07       0  4983.9    0.05       0  4987.9    0.07       0
Bank Sta=4983.9,4987.9
Exp/Cntr=0.3,0.1

Type RM Length L Ch R = 1,1700,216,216,216
BEGIN DESCRIPTION:
Stream0296 3.1
END DESCRIPTION:
XS GIS Cut Line= 3
      1856214.44     13908519.38      1856007.60     13908709.03
      1855944.52     13908861.25
#Sta/Elev= 30
  4791.8 1998.87  4816.9 1994.32  4866.2 1987.88  4915.5 1976.95  4922.9 1975.96
  4929.7 1973.34  4936.8 1971.61  4943.9 1968.79  4972.2 1960.20  4991.8 1957.51
  4992.1 1957.01  4995.6 1957.01  4995.8 1957.51  5008.0 1957.61  5014.8 1958.46
  5029.0 1957.52  5035.8 1958.17  5043.2 1957.79  5057.3 1959.14  5070.8 1961.51
  5088.3 1966.73  5093.7 1967.43  5111.4 1971.64  5117.6 1973.95  5141.5 1978.86
  5165.4 1982.56  5176.3 1985.16  5187.1 1986.47  5194.7 1988.25  5237.2 1994.01
#Mann=4,-1,0
  4791.8     0.1       0  4936.8    0.07       0  4991.8    0.05       0
  4995.8    0.07       0
Bank Sta=4991.8,4995.8
Exp/Cntr=0.3,0.1

Type RM Length L Ch R = 1,1484,469,469,469
BEGIN DESCRIPTION:
Stream0296 3.0
END DESCRIPTION:
XS GIS Cut Line= 3
      1856104.56     13908395.27      1855875.00     13908575.00
      1855825.02     13908674.96
#Sta/Elev= 30
  4708.2 1991.83  4750.2 1990.02  4771.1 1988.03  4779.1 1986.64  4821.9 1983.06
  4828.9 1981.19  4872.2 1975.34  4878.6 1973.06  4896.3 1968.76  4907.5 1966.23
  4913.9 1963.36  4928.3 1959.36  4942.8 1955.96  4949.1 1952.77  4963.6 1948.18
  4986.2 1942.87  4994.6 1942.55  4994.8 1942.05  4998.3 1942.05  4998.6 1942.55
  5002.5 1942.55  5013.7 1944.23  5027.7 1949.95  5030.5 1952.10  5044.5 1957.43
  5052.9 1958.60  5075.2 1964.89  5103.2 1970.58  5108.8 1972.30  5111.5 1972.30
#Mann=4,-1,0
  4708.2     0.1       0  4896.3    0.07       0  4994.6    0.05       0
  4998.6    0.07       0
Bank Sta=4994.6,4998.6
Exp/Cntr=0.3,0.1

Type RM Length L Ch R = 1,1015,475,475,475
BEGIN DESCRIPTION:
Stream0296 2.0
END DESCRIPTION:
XS GIS Cut Line= 3
      1855714.40     13907985.80      1855525.00     13908275.00
      1855525.00     13908375.00
#Sta/Elev= 30
  4654.0 1999.32  4702.7 1994.54  4790.2 1983.48  4796.5 1981.67  4826.3 1977.13
  4832.3 1974.86  4856.3 1970.19  4862.5 1967.97  4877.6 1964.57  4886.8 1961.57
  4898.7 1958.49  4904.7 1957.87  4919.8 1951.82  4928.0 1949.97  4940.9 1939.37
  4956.0 1934.71  4971.1 1932.29  4986.2 1931.11  4990.1 1929.71  4990.4 1929.21
  4993.9 1929.21  4994.1 1929.71  4996.7 1930.44  5009.7 1931.12  5019.7 1932.91
  5049.7 1943.38  5069.7 1948.61  5089.7 1950.82  5097.2 1952.50  5099.7 1952.50
#Mann=4,-1,0
  4654.0     0.1       0  4886.8    0.07       0  4990.1    0.05       0
  4994.1    0.07       0
Bank Sta=4990.1,4994.1
Exp/Cntr=0.3,0.1

Type RM Length L Ch R = 1,540,339,339,339
BEGIN DESCRIPTION:
Stream0296 1.0
END DESCRIPTION:
XS GIS Cut Line= 3
      1855324.97     13907925.02      1855125.00     13908075.00
      1855074.98     13908175.03
#Sta/Elev= 30
  4754.4 1960.30  4767.9 1958.88  4790.8 1958.14  4797.1 1957.47  4806.0 1955.34
  4811.7 1952.84  4826.2 1950.50  4840.8 1949.16  4847.1 1947.05  4854.4 1942.84
  4876.2 1935.46  4882.5 1933.88  4904.4 1930.27  4932.5 1928.59  4940.8 1926.22
  4954.4 1923.64  4967.9 1923.24  4988.8 1921.05  4989.1 1920.55  4992.6 1920.55
  4992.8 1921.05  5001.2 1927.57  5007.2 1927.57  5018.3 1932.35  5035.1 1935.93
  5063.1 1946.30  5071.4 1948.20  5107.8 1952.40  5113.4 1955.22  5116.2 1955.22
#Mann=4,-1,0
  4754.4     0.1       0  4806.0    0.07       0  4988.8    0.05       0
  4992.8    0.07       0
Bank Sta=4988.8,4992.8
Exp/Cntr=0.3,0.1

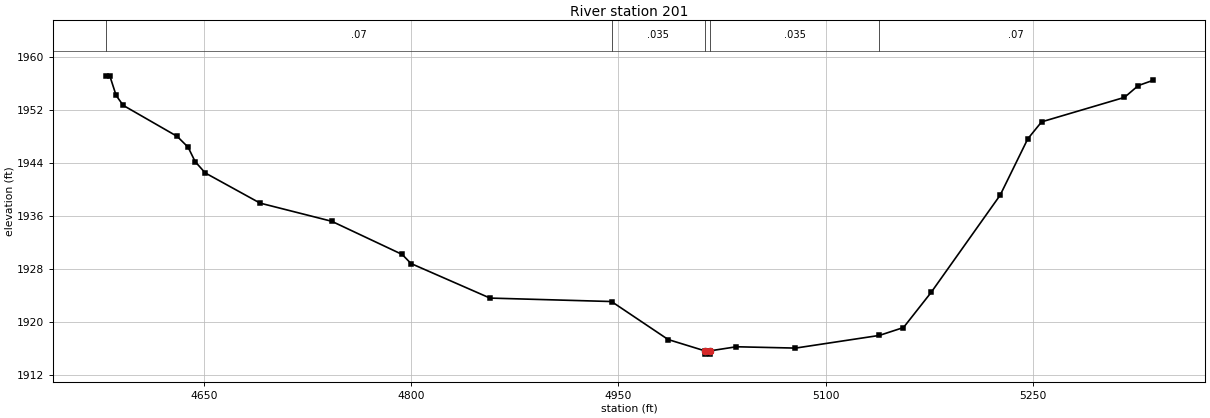
Type RM Length L Ch R = 1,201,0,0,0
BEGIN DESCRIPTION:
Stream0296 0.0
END DESCRIPTION:
XS GIS Cut Line= 4
      1855305.74     13907801.71      1855002.59     13907743.81
      1854832.80     13907890.31      1854831.65     13908115.72
#Sta/Elev= 30
  4578.8 1957.12  4581.7 1957.12  4586.3 1954.16  4591.4 1952.67  4630.5 1947.99
  4638.4 1946.36  4643.5 1944.19  4650.8 1942.48  4690.5 1937.93  4742.4 1935.19
  4793.4 1930.19  4799.8 1928.82  4857.0 1923.61  4945.0 1923.09  4986.0 1917.36
  5012.5 1915.66  5012.8 1915.16  5016.3 1915.16  5016.5 1915.66  5035.4 1916.27
  5078.2 1916.07  5138.9 1917.98  5156.4 1919.17  5176.4 1924.46  5226.4 1939.13
  5246.4 1947.62  5256.4 1950.18  5316.4 1953.87  5326.4 1955.65  5337.1 1956.44
#Mann=5,-1,0
  4578.8    0.07       0  4945.0   0.035       0  5012.5   0.035       0
  5016.5   0.035       0  5138.9    0.07       0
Bank Sta=5012.5,5016.5
Exp/Cntr=0.3,0.1

Chan Stop Cuts=-1