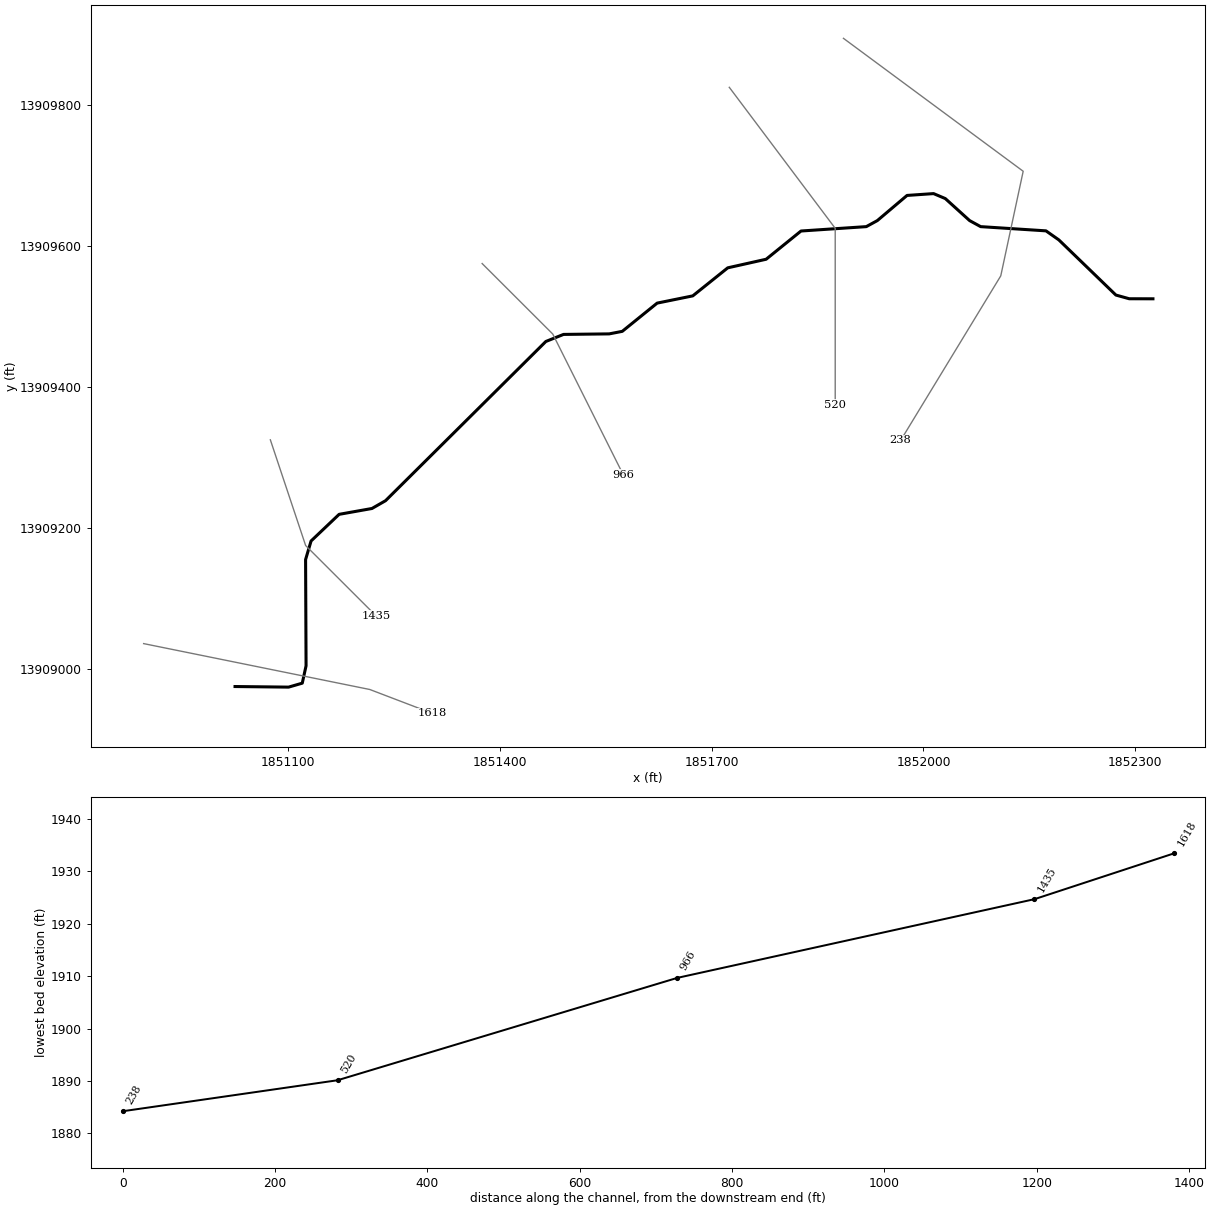
--- Stream0298.prj (project) ---

Proj Title=Stream0298 Base Level Engineering
Current Plan=p01
Default Exp/Contr=0.3,0.1
English Units
Geom File=g01
Flow File=f01
Plan File=p01
Y Axis Title=Elevation
X Axis Title(PF)=Main Channel Distance
X Axis Title(XS)=Station
BEGIN DESCRIPTION:
Stream0298
END DESCRIPTION:
DSS Export Rating Curves= 0
DSS Export Rating Curve Sorted= 0
DSS Export Volume Flow Curves= 0
DXF OffsetX= 0
DXF OffsetY= 0
DXF ScaleX= 1
DXF ScaleY= 10

--- Stream0298.p01 (plan) ---

Plan Title=Multiple Run
Short Identifier=Multiple
Geom File=g01
Flow File=f01
Subcritical Flow
K Sum by GR= 0
Std Step Tol= 0.01
Critical Tol= 0.01
Num of Std Step Trials= 20
Max Error Tol= 0.3
Flow Tol Ratio= 0.001
Split Flow NTrial= 30
Split Flow Tol= 0.02
Split Flow Ratio= 0.02
Log Output Level= 0
Friction Slope Method= 1
Unsteady Friction Slope Method= 2
Unsteady Bridges Friction Slope Method= 1
Parabolic Critical Depth
Global Vel Dist=  1 , 1 , 1
Global Log Level= 0
CheckData=True
Encroach Param= -1, 0, 0, 0
BEGIN DESCRIPTION:
Multiple Run
END DESCRIPTION:

--- Stream0298.f01 (steady flow) ---

Flow Title=Multiple
Program Version=4.10
Number of Profiles= 7
Profile Names=10-year,25-year,50-year,1pct_min,100-year,1pct_plu,500-year
River Rch & RM=Stream0298,Reach-1         ,1618
     487     801    1092     724    1444    2881    2486
Boundary for River Rch & Prof#=Stream0298,Reach-1         , 1
Up Type= 0
Dn Type= 3
Dn Slope=0.01
Boundary for River Rch & Prof#=Stream0298,Reach-1         , 2
Up Type= 0
Dn Type= 3
Dn Slope=0.01
Boundary for River Rch & Prof#=Stream0298,Reach-1         , 3
Up Type= 0
Dn Type= 3
Dn Slope=0.01
Boundary for River Rch & Prof#=Stream0298,Reach-1         , 4
Up Type= 0
Dn Type= 3
Dn Slope=0.01
Boundary for River Rch & Prof#=Stream0298,Reach-1         , 5
Up Type= 0
Dn Type= 3
Dn Slope=0.01
Boundary for River Rch & Prof#=Stream0298,Reach-1         , 6
Up Type= 0
Dn Type= 3
Dn Slope=0.01
Boundary for River Rch & Prof#=Stream0298,Reach-1         , 7
Up Type= 0
Dn Type= 3
Dn Slope=0.01
DSS Import GetInterval= 0
DSS Import GetPeak= 0
DSS Import FillOption= 0

--- Stream0298.g01 (geometry) ---

Geom Title=Existing Conditions

River Reach=Stream0298,Reach-1
Reach XY= 30
      1851025.00     13908975.00      1851100.84     13908974.16
      1851120.22     13908979.78      1851125.59     13909004.41
      1851124.92     13909155.12      1851132.69     13909181.48
      1851172.42     13909219.26      1851218.91     13909227.55
      1851238.20     13909238.64      1851465.21     13909464.48
      1851490.22     13909474.48      1851554.90     13909475.24
      1851573.41     13909478.83      1851622.82     13909518.88
      1851673.28     13909529.16      1851722.80     13909568.92
      1851777.18     13909581.12      1851826.58     13909621.17
      1851919.03     13909627.38      1851934.65     13909635.95
      1851976.73     13909671.63      1852014.31     13909674.23
      1852030.92     13909667.19      1852065.35     13909635.95
      1852080.97     13909627.38      1852173.50     13909621.39
      1852191.75     13909608.54      1852272.49     13909530.33
      1852291.37     13909525.08      1852325.00     13909525.00

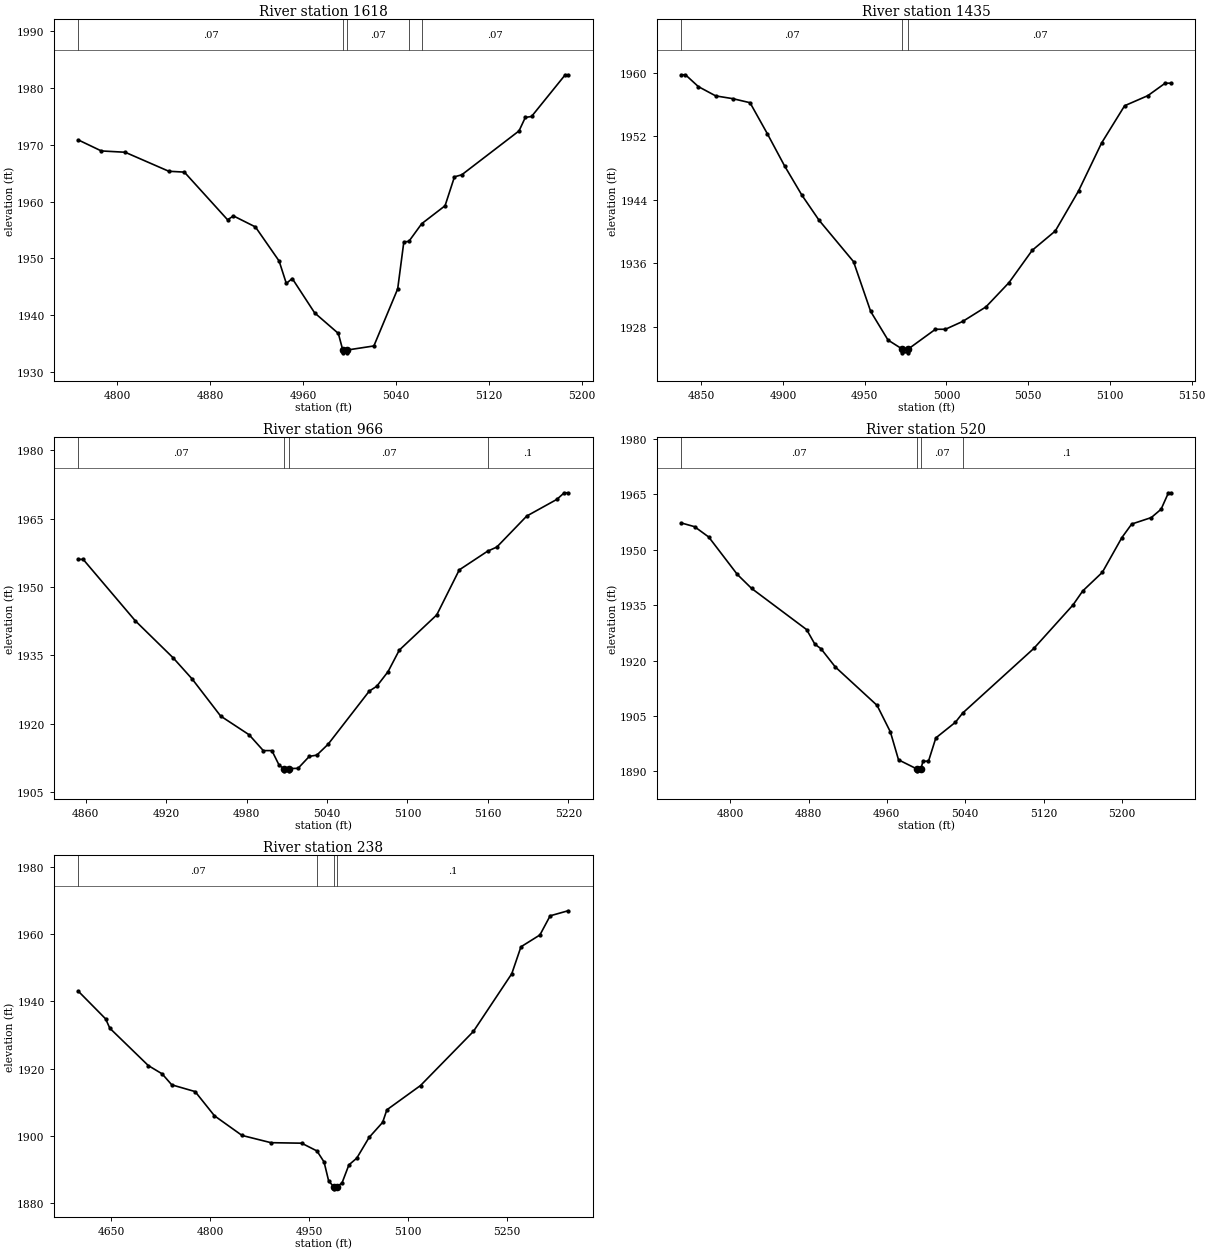
Type RM Length L Ch R = 1,1618,183,183,183
BEGIN DESCRIPTION:
Stream0298 4.0
END DESCRIPTION:
XS GIS Cut Line= 3
      1850895.55     13909035.89      1851215.86     13908970.79
      1851304.45     13908936.92
#Sta/Elev= 30
  4766.6 1970.82  4786.4 1968.89  4806.9 1968.66  4844.5 1965.32  4857.9 1965.17
  4895.1 1956.80  4900.2 1957.47  4919.1 1955.54  4939.5 1949.55  4945.7 1945.61
  4950.8 1946.48  4970.1 1940.44  4990.5 1936.83  4994.3 1933.92  4994.6 1933.42
  4998.1 1933.42  4998.3 1933.92  5021.1 1934.63  5041.6 1944.65  5046.9 1952.91
  5051.2 1952.99  5062.3 1956.11  5082.4 1959.26  5090.5 1964.34  5096.8 1964.70
  5146.1 1972.41  5151.5 1974.77  5156.9 1974.95  5185.9 1982.27  5188.3 1982.27
#Mann=5,-1,0
  4766.6    0.07       0  4994.3    0.05       0  4998.3    0.07       0
  5051.2     0.1       0  5062.3    0.07       0
Bank Sta=4994.3,4998.3
Exp/Cntr=0.3,0.1

Type RM Length L Ch R = 1,1435,469,469,469
BEGIN DESCRIPTION:
Stream0298 3.0
END DESCRIPTION:
XS GIS Cut Line= 3
      1851075.01     13909324.98      1851125.00     13909175.00
      1851224.99     13909075.01
#Sta/Elev= 30
  4837.8 1959.72  4840.4 1959.72  4848.3 1958.23  4858.9 1957.06  4869.4 1956.71
  4879.9 1956.20  4890.5 1952.29  4901.0 1948.25  4911.6 1944.56  4922.1 1941.40
  4943.2 1936.18  4953.7 1929.90  4964.3 1926.30  4972.8 1925.19  4973.1 1924.69
  4976.6 1924.69  4976.8 1925.19  4993.3 1927.66  4999.4 1927.66  5010.0 1928.65
  5024.2 1930.48  5038.3 1933.54  5052.5 1937.61  5066.6 1940.04  5080.8 1945.08
  5094.9 1951.12  5109.0 1955.82  5123.2 1957.09  5133.8 1958.66  5137.3 1958.66
#Mann=3,-1,0
  4837.8    0.07       0  4972.8    0.05       0  4976.8    0.07       0
Bank Sta=4972.8,4976.8
Exp/Cntr=0.3,0.1

Type RM Length L Ch R = 1,966,446,446,446
BEGIN DESCRIPTION:
Stream0298 2.0
END DESCRIPTION:
XS GIS Cut Line= 3
      1851374.97     13909575.03      1851475.00     13909475.00
      1851575.01     13909274.97
#Sta/Elev= 30
  4854.6 1956.07  4858.2 1956.07  4897.1 1942.58  4925.4 1934.43  4939.5 1929.81
  4960.7 1921.69  4981.9 1917.59  4992.5 1914.11  4998.9 1914.11  5004.4 1910.85
  5008.0 1910.17  5008.3 1909.67  5011.8 1909.67  5012.0 1910.17  5018.4 1910.22
  5026.8 1912.84  5032.4 1913.12  5040.8 1915.50  5071.5 1927.16  5077.1 1928.23
  5085.5 1931.43  5093.9 1936.16  5121.8 1943.88  5138.6 1953.76  5159.7 1957.86
  5166.6 1958.77  5188.9 1965.57  5211.3 1969.22  5216.9 1970.68  5219.7 1970.68
#Mann=4,-1,0
  4854.6    0.07       0  5008.0    0.05       0  5012.0    0.07       0
  5159.7     0.1       0
Bank Sta=5008,5012
Exp/Cntr=0.3,0.1

Type RM Length L Ch R = 1,520,282,282,282
BEGIN DESCRIPTION:
Stream0298 1.0
END DESCRIPTION:
XS GIS Cut Line= 3
      1851724.99     13909825.01      1851875.00     13909625.00
      1851875.00     13909375.01
#Sta/Elev= 30
  4750.0 1957.24  4763.6 1956.23  4778.1 1953.43  4807.3 1943.30  4821.9 1939.51
  4878.1 1928.36  4886.5 1924.41  4892.7 1923.20  4907.3 1918.27  4950.0 1907.86
  4963.6 1900.67  4971.9 1893.12  4990.7 1890.64  4991.0 1890.14  4994.7 1890.64
  4996.9 1892.75  5002.5 1892.75  5010.0 1899.05  5030.0 1903.29  5037.4 1905.78
  5110.0 1923.26  5150.0 1935.02  5160.0 1938.83  5180.0 1943.87  5200.0 1953.29
  5210.0 1956.94  5230.0 1958.69  5240.0 1960.95  5247.5 1965.40  5250.0 1965.40
#Mann=4,-1,0
  4750.0    0.07       0  4990.7    0.05       0  4994.7    0.07       0
  5037.4     0.1       0
Bank Sta=4990.7,4994.7
Exp/Cntr=0.3,0.1

Type RM Length L Ch R = 1,238,0,0,0
BEGIN DESCRIPTION:
Stream0298 0.0
END DESCRIPTION:
XS GIS Cut Line= 4
      1851886.68     13909894.48      1852141.22     13909705.93
      1852109.47     13909557.53      1851967.64     13909324.06
#Sta/Elev= 30
  4600.5 1943.05  4641.8 1934.83  4648.2 1932.04  4706.5 1920.92  4727.4 1918.46
  4742.0 1915.19  4777.4 1913.18  4806.7 1905.97  4848.4 1900.13  4892.2 1897.97
  4938.7 1897.82  4961.9 1895.51  4972.7 1892.22  4979.6 1886.60  4987.8 1884.73
  4988.1 1884.23  4991.8 1884.73  5000.0 1886.05  5010.3 1891.36  5022.2 1893.36
  5040.9 1899.53  5061.4 1904.02  5067.8 1907.75  5118.8 1914.99  5198.8 1931.07
  5257.0 1948.27  5270.9 1956.28  5299.6 1959.80  5315.1 1965.50  5342.2 1967.00
#Mann=4,-1,0
  4600.5    0.07       0  4961.9     0.1       0  4987.8    0.05       0
  4991.8     0.1       0
Bank Sta=4987.8,4991.8
Exp/Cntr=0.3,0.1

Chan Stop Cuts=-1