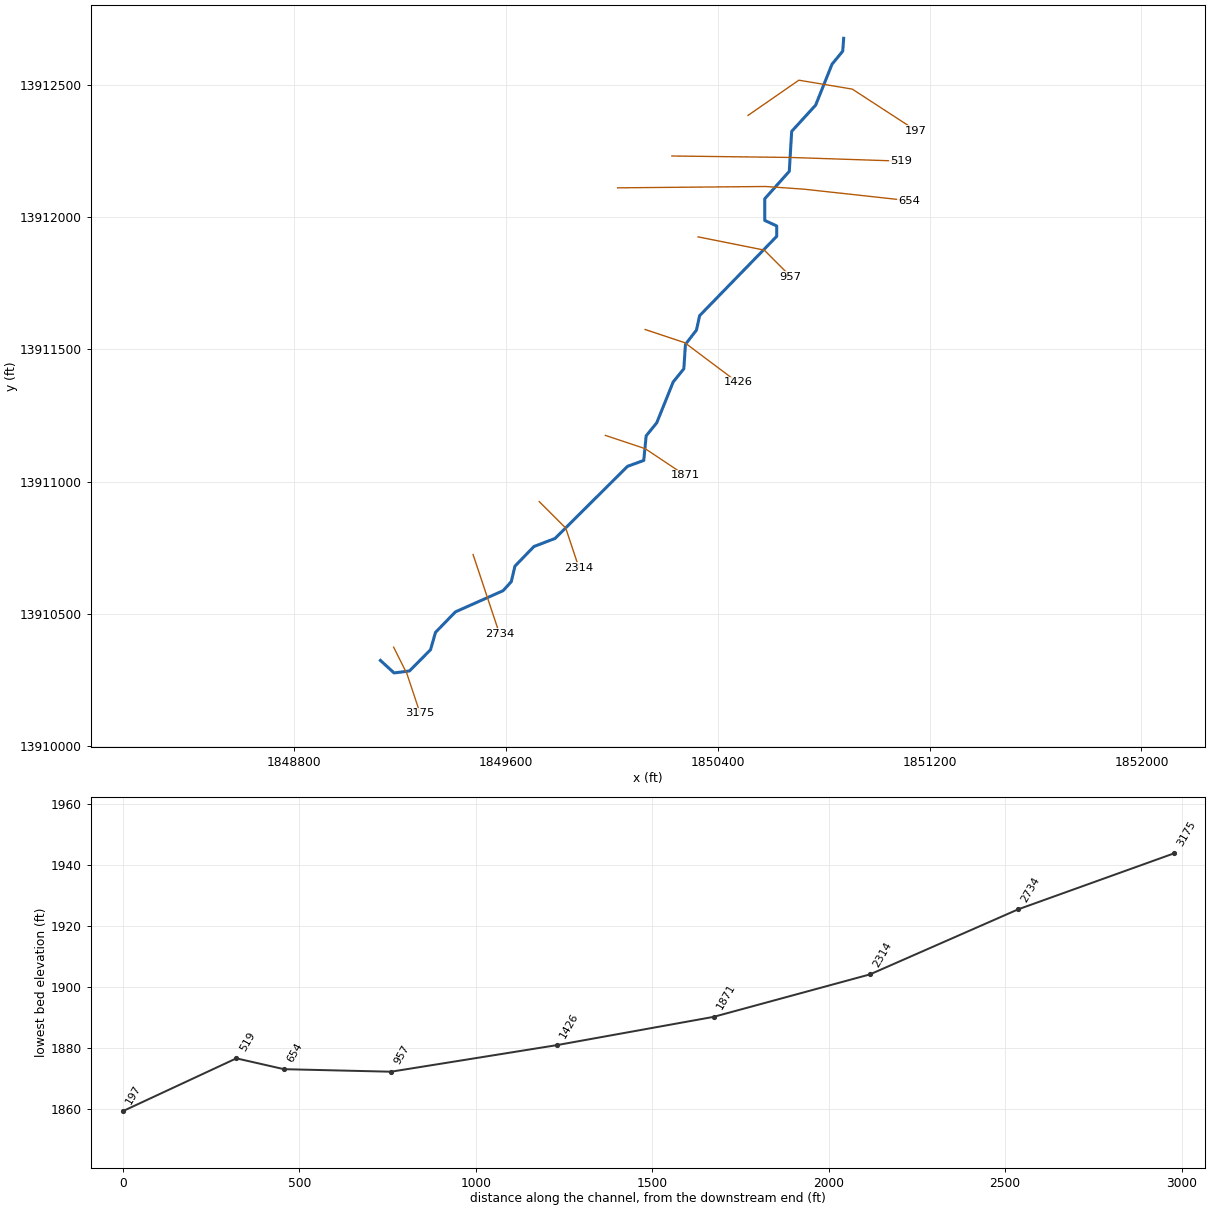
--- Stream0301.prj (project) ---

Proj Title=Stream0301 Base Level Engineering
Current Plan=p01
Default Exp/Contr=0.3,0.1
English Units
Geom File=g01
Flow File=f01
Plan File=p01
Y Axis Title=Elevation
X Axis Title(PF)=Main Channel Distance
X Axis Title(XS)=Station
BEGIN DESCRIPTION:
Stream0301
END DESCRIPTION:
DSS Export Rating Curves= 0
DSS Export Rating Curve Sorted= 0
DSS Export Volume Flow Curves= 0
DXF OffsetX= 0
DXF OffsetY= 0
DXF ScaleX= 1
DXF ScaleY= 10

--- Stream0301.p01 (plan) ---

Plan Title=Multiple Run
Short Identifier=Multiple
Geom File=g01
Flow File=f01
Subcritical Flow
K Sum by GR= 0
Std Step Tol= 0.01
Critical Tol= 0.01
Num of Std Step Trials= 20
Max Error Tol= 0.3
Flow Tol Ratio= 0.001
Split Flow NTrial= 30
Split Flow Tol= 0.02
Split Flow Ratio= 0.02
Log Output Level= 0
Friction Slope Method= 1
Unsteady Friction Slope Method= 2
Unsteady Bridges Friction Slope Method= 1
Parabolic Critical Depth
Global Vel Dist=  1 , 1 , 1
Global Log Level= 0
CheckData=True
Encroach Param= -1, 0, 0, 0
BEGIN DESCRIPTION:
Multiple Run
END DESCRIPTION:

--- Stream0301.f01 (steady flow) ---

Flow Title=Multiple
Program Version=4.10
Number of Profiles= 7
Profile Names=10-year,25-year,50-year,1pct_min,100-year,1pct_plu,500-year
River Rch & RM=Stream0301,Reach-1         ,3175
     530     876    1197     795    1586    3163    2740
Boundary for River Rch & Prof#=Stream0301,Reach-1         , 1
Up Type= 0
Dn Type= 3
Dn Slope=0.01
Boundary for River Rch & Prof#=Stream0301,Reach-1         , 2
Up Type= 0
Dn Type= 3
Dn Slope=0.01
Boundary for River Rch & Prof#=Stream0301,Reach-1         , 3
Up Type= 0
Dn Type= 3
Dn Slope=0.01
Boundary for River Rch & Prof#=Stream0301,Reach-1         , 4
Up Type= 0
Dn Type= 3
Dn Slope=0.01
Boundary for River Rch & Prof#=Stream0301,Reach-1         , 5
Up Type= 0
Dn Type= 3
Dn Slope=0.01
Boundary for River Rch & Prof#=Stream0301,Reach-1         , 6
Up Type= 0
Dn Type= 3
Dn Slope=0.01
Boundary for River Rch & Prof#=Stream0301,Reach-1         , 7
Up Type= 0
Dn Type= 3
Dn Slope=0.01
DSS Import GetInterval= 0
DSS Import GetPeak= 0
DSS Import FillOption= 0

--- Stream0301.g01 (geometry) ---

Geom Title=Existing Conditions
Program Version=4.10

River Reach=Stream0301      ,Reach-1
Reach XY= 30
        1849125.       13910325.      1849176.62     13910277.67
      1849234.73     13910285.18      1849314.23      13910365.3
      1849333.15     13910431.06      1849408.29     13910508.37
      1849588.57     13910588.47      1849619.25     13910622.46
      1849633.16     13910681.05      1849704.87     13910755.23
      1849784.68     13910785.78      1850058.55     13911058.26
      1850119.74     13911080.47      1850128.86     13911173.34
      1850168.89     13911222.82      1850231.12     13911377.18
      1850271.17     13911426.58      1850277.33     13911519.03
      1850318.86     13911572.83      1850330.83      13911627.3
      1850621.97     13911926.98      1850622.01     13911966.34
       1850576.9       13911987.      1850576.94     13912069.02
      1850669.52     13912172.56      1850678.55     13912323.53
      1850769.15     13912422.71      1850830.95     13912577.25
       1850871.4     13912626.49        1850875.       13912675.

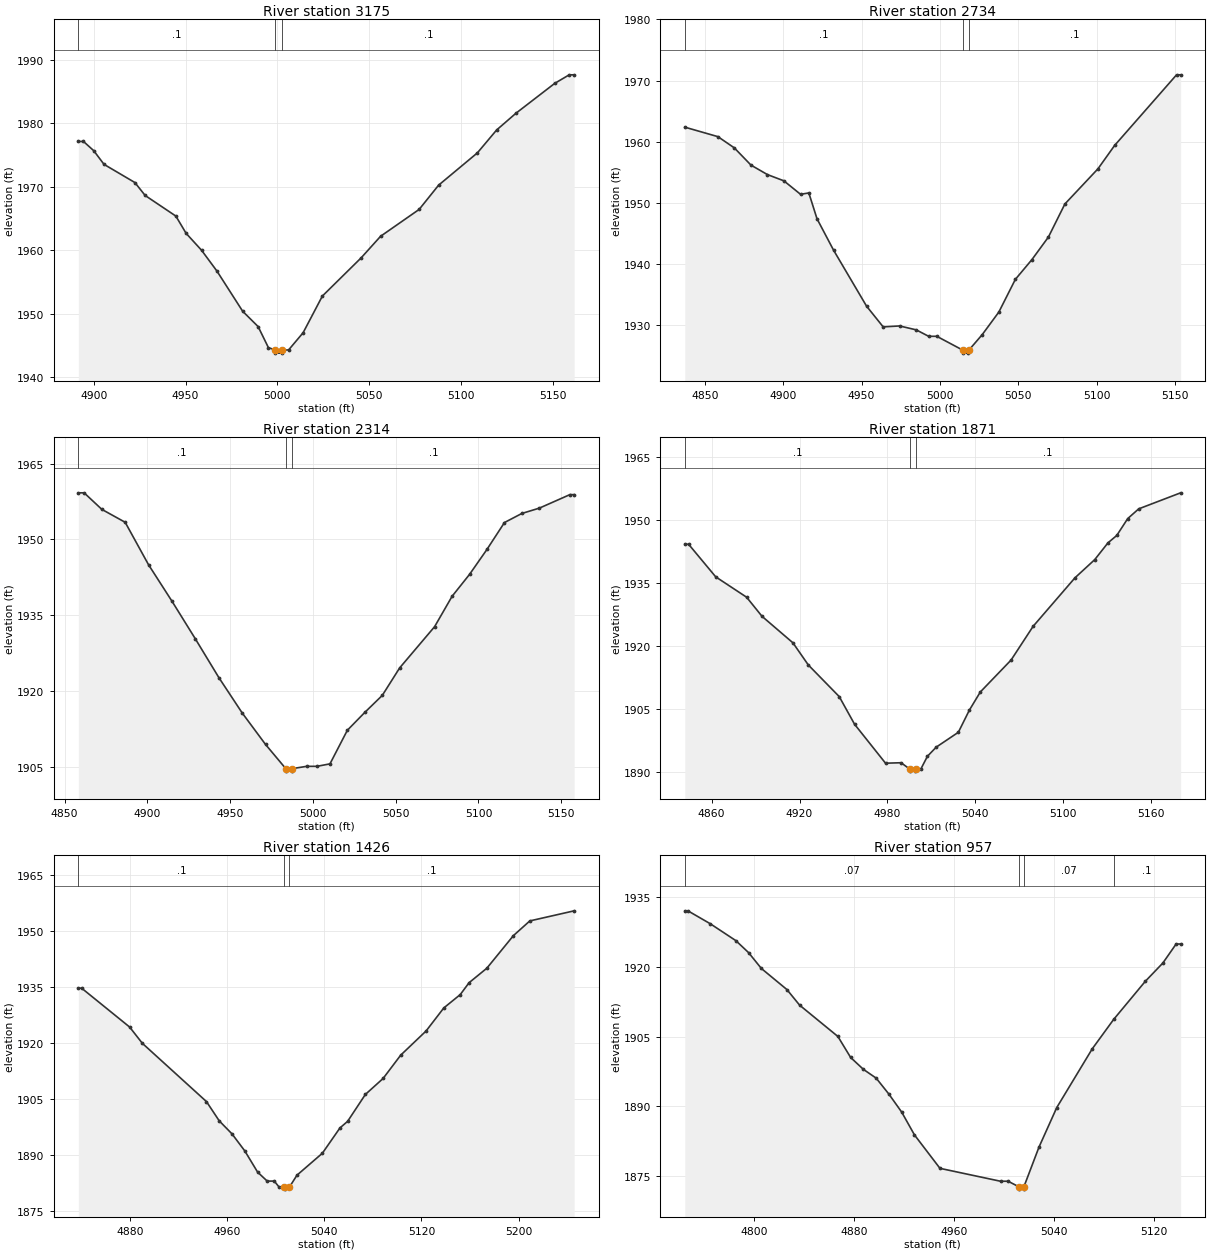
Type RM Length L Ch R = 1 ,3175    ,441,441,441
BEGIN DESCRIPTION:
Stream0301 7.0
END DESCRIPTION:
XS GIS Cut Line= 3
      1849174.98     13910375.04        1849225.       13910275.
      1849275.01     13910124.96
#Sta/Elev= 30
  4891.6 1977.15  4894.4 1977.15    4900 1975.69  4905.6 1973.54  4922.4 1970.68
    4928 1968.64  4944.7  1965.4  4950.3 1962.68  4958.7 1960.02  4967.1 1956.73
  4981.1 1950.41  4989.5    1948  4995.1 1944.69  4998.7 1944.32  4998.9 1943.82
  5002.4 1943.82  5002.7 1944.32  5006.1 1944.32    5014 1947.03  5024.5 1952.81
  5045.6 1958.82  5056.2 1962.22  5077.2 1966.45  5087.8 1970.27  5108.9 1975.35
  5119.4 1978.96  5129.9 1981.59    5151 1986.29  5158.9 1987.64  5161.6 1987.64
#Mann= 3 ,-1 , 0
  4891.6      .1       0  4998.7     .05       0  5002.7      .1       0
Bank Sta=4998.7,5002.7
XS Rating Curve= 0 ,0
Exp/Cntr=0.3,0.1

Type RM Length L Ch R = 1 ,2734    ,420,420,420
BEGIN DESCRIPTION:
Stream0301 6.0
END DESCRIPTION:
XS GIS Cut Line= 3
        1849475.       13910725.        1849525.       13910575.
      1849574.99     13910425.02
#Sta/Elev= 30
  4837.3 1962.38  4858.4 1960.83  4868.9 1958.99  4879.5 1956.18    4890 1954.63
  4900.5 1953.61  4911.1 1951.41  4916.4 1951.63  4921.6 1947.42  4932.2 1942.27
  4953.2 1933.14  4963.8 1929.75  4974.3  1929.9  4984.9 1929.26  4992.8 1928.21
    4998 1928.21  5014.5 1925.96  5014.7 1925.46  5018.2 1925.46  5018.5 1925.96
    5027 1928.49  5037.6 1932.18  5048.1 1937.51  5058.7 1940.75  5069.2 1944.43
  5079.7 1949.83  5100.8 1955.58  5111.4 1959.39  5150.9 1970.93  5153.5 1970.93
#Mann= 3 ,-1 , 0
  4837.3      .1       0  5014.5     .05       0  5018.5      .1       0
Bank Sta=5014.5,5018.5
XS Rating Curve= 0 ,0
Exp/Cntr=0.3,0.1

Type RM Length L Ch R = 1 ,2314    ,443,443,443
BEGIN DESCRIPTION:
Stream0301 5.0
END DESCRIPTION:
XS GIS Cut Line= 3
      1849724.99     13910925.01        1849825.       13910825.
      1849874.99     13910675.04
#Sta/Elev= 30
  4858.3 1959.25  4861.8 1959.25  4872.5 1955.97  4886.6 1953.41  4900.7    1945
  4914.9 1937.75    4929  1930.3  4943.2 1922.62  4957.3 1915.61  4971.4 1909.37
  4983.6 1904.59  4983.8 1904.09  4987.3 1904.09  4987.6 1904.59  4996.2 1905.04
  5002.4 1905.04  5010.3 1905.53  5020.8 1912.19  5031.4 1915.75  5041.9  1919.1
  5052.4 1924.55  5073.5 1932.72  5084.1 1938.76  5094.6 1943.08  5105.1 1948.02
  5115.7 1953.36  5126.2 1955.16  5136.8 1956.22  5155.2 1958.89  5157.8 1958.89
#Mann= 3 ,-1 , 0
  4858.3      .1       0  4983.6     .05       0  4987.6      .1       0
Bank Sta=4983.6,4987.6
XS Rating Curve= 0 ,0
Exp/Cntr=0.3,0.1

Type RM Length L Ch R = 1 ,1871    ,445,445,445
BEGIN DESCRIPTION:
Stream0301 4.0
END DESCRIPTION:
XS GIS Cut Line= 3
        1849975.       13911175.        1850125.       13911125.
      1850275.01     13911024.99
#Sta/Elev= 30
  4841.7 1944.23  4844.3 1944.23  4862.8 1936.46  4883.9  1931.6  4894.4 1927.05
  4915.5 1920.73    4926 1915.45  4947.1 1907.91  4957.6  1901.3  4978.7 1892.03
  4989.3 1892.14  4995.2 1890.64  4995.4 1890.14  4998.9 1890.14  4999.2 1890.64
  5002.8 1890.64  5007.3 1893.68  5013.3 1895.86  5028.4  1899.4  5035.9 1904.67
  5043.4 1909.01  5064.4 1916.63  5079.4 1924.65    5108 1936.23  5121.5 1940.57
  5130.5 1944.56  5136.5 1946.32    5144 1950.35  5151.5 1952.67  5180.1 1956.49
#Mann= 3 ,-1 , 0
  4841.7      .1       0  4995.2     .05       0  4999.2      .1       0
Bank Sta=4995.2,4999.2
XS Rating Curve= 0 ,0
Exp/Cntr=0.3,0.1

Type RM Length L Ch R = 1 ,1426    ,469,469,469
BEGIN DESCRIPTION:
Stream0301 3.0
END DESCRIPTION:
XS GIS Cut Line= 3
      1850124.96     13911575.01        1850275.       13911525.
      1850475.04     13911374.97
#Sta/Elev= 30
  4837.5 1934.62  4840.2 1934.62  4879.7 1924.22  4890.2 1919.86    4943 1904.26
  4953.5 1899.11    4964 1895.63  4974.6 1891.04  4985.1 1885.39    4993 1882.99
  4998.8 1882.99  5002.9 1881.35  5007.2 1881.34  5007.4 1880.84  5011.2 1881.34
  5017.5 1884.57  5038.4 1890.44  5052.9 1897.22  5059.2 1898.98  5073.8 1906.17
  5088.4 1910.45  5102.9 1916.69  5123.8 1923.16  5138.4 1929.33  5151.9 1932.89
  5159.2 1936.08  5173.8 1939.95  5195.7 1948.68  5209.2 1952.61  5245.7 1955.31
#Mann= 3 ,-1 , 0
  4837.5      .1       0  5007.2     .05       0  5011.2      .1       0
Bank Sta=5007.2,5011.2
XS Rating Curve= 0 ,0
Exp/Cntr=0.3,0.1

Type RM Length L Ch R = 1 ,957     ,303,303,303
BEGIN DESCRIPTION:
Stream0301 2.0
END DESCRIPTION:
XS GIS Cut Line= 3
        1850325.       13911925.        1850575.       13911875.
      1850675.02     13911774.98
#Sta/Elev= 30
  4744.8 1932.11  4747.3 1932.11  4765.2 1929.32  4785.6 1925.69  4795.8  1923.1
    4806 1919.69  4826.4 1915.15  4836.6 1911.78  4867.2 1905.03  4877.4  1900.5
  4887.6 1897.94  4897.8 1896.05    4908  1892.6  4918.2 1888.73  4928.4 1883.82
  4948.8 1876.61  4997.2 1873.83  5003.3 1873.83  5011.9 1872.63  5012.1 1872.13
  5015.6 1872.13  5015.9 1872.63    5028 1881.21  5042.2 1889.72  5070.5 1902.35
  5087.7 1908.72  5112.9  1916.9    5127 1920.86  5137.6 1924.96  5141.2 1924.96
#Mann= 4 ,-1 , 0
  4744.8     .07       0  5011.9     .05       0  5015.9     .07       0
  5087.7      .1       0
Bank Sta=5011.9,5015.9
XS Rating Curve= 0 ,0
Exp/Cntr=0.3,0.1

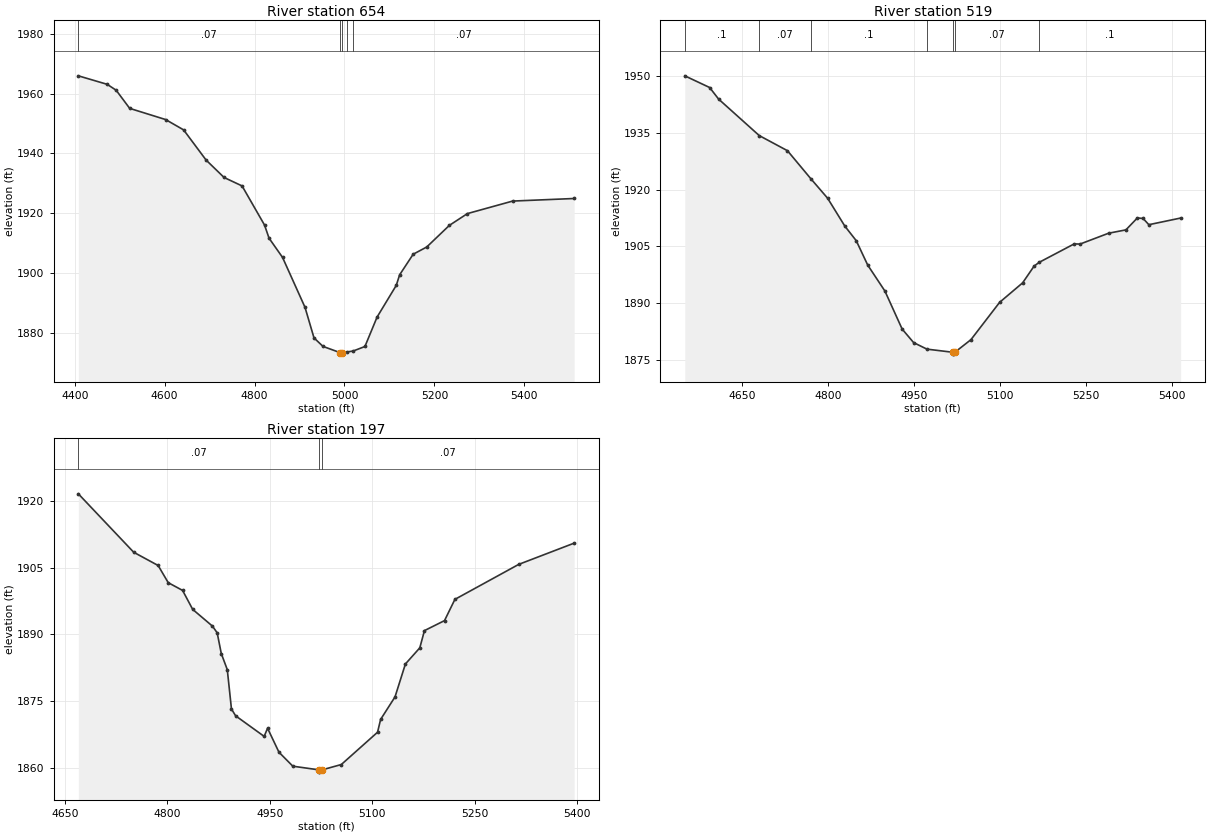
Type RM Length L Ch R = 1 ,654     ,135,135,135
BEGIN DESCRIPTION:
Stream0301 1.1
END DESCRIPTION:
XS GIS Cut Line= 4
      1850020.78     13912110.27      1850579.88      13912115.3
      1850725.14     13912105.21      1851120.94     13912061.84
#Sta/Elev= 30
    4408 1965.93  4472.2 1963.09  4492.2 1961.11  4522.2 1955.06  4602.2 1951.32
  4642.2 1947.87  4692.2 1937.79  4732.2 1931.97  4772.2 1929.15  4822.2 1916.07
  4832.2  1911.7  4862.2 1905.28  4912.2  1888.6  4932.2 1878.39  4952.2 1875.54
  4990.3 1873.46  4990.6 1872.96  4994.3 1873.46  5004.9 1873.67  5019.2 1873.99
  5045.5 1875.51  5072.5 1885.33  5115.2 1895.93  5122.7 1899.46  5152.8 1906.33
    5183 1908.75  5233.3 1915.97  5273.5 1919.91  5374.1 1924.09  5510.9 1924.95
#Mann= 5 ,-1 , 0
    4408     .07       0  4990.3     .05       0  4994.3     .07       0
  5004.9      .1       0  5019.2     .07       0
Bank Sta=4990.3,4994.3
XS Rating Curve= 0 ,0
Exp/Cntr=0.3,0.1

Type RM Length L Ch R = 1 ,519     ,322,322,322
BEGIN DESCRIPTION:
Stream0301 1.0
END DESCRIPTION:
XS GIS Cut Line= 3
      1850226.05     13912230.52        1850675.       13912225.
      1851090.38     13912211.13
#Sta/Elev= 30
  4550.7 1950.12    4594 1947.03  4609.7 1943.96  4680.5 1934.32  4729.7 1930.32
  4770.3 1922.94  4799.7 1917.76  4829.7 1910.39  4849.7 1906.51  4869.7 1900.06
  4899.7 1893.19  4929.7 1883.15  4949.7 1879.57  4972.9 1877.84  5017.7 1877.02
  5017.9 1876.52  5021.7 1877.02  5049.7 1880.35  5099.7 1890.22  5139.8 1895.37
  5159.8  1899.8  5168.6 1900.79  5229.8 1905.68  5239.8 1905.62  5289.8  1908.5
  5319.9 1909.38  5339.9 1912.54  5349.9 1912.39  5359.9 1910.75  5415.3 1912.51
#Mann= 7 ,-1 , 0
  4550.7      .1       0  4680.5     .07       0  4770.3      .1       0
  4972.9     .07       0  5017.7     .05       0  5021.7     .07       0
  5168.6      .1       0
Bank Sta=5017.7,5021.7
XS Rating Curve= 0 ,0
Exp/Cntr=0.3,0.1

Type RM Length L Ch R = 1 ,197     ,0,0,0
BEGIN DESCRIPTION:
Stream0301 0.0
END DESCRIPTION:
XS GIS Cut Line= 4
      1850513.51     13912383.72      1850705.69     13912516.89
      1850907.42     13912483.25      1851148.83     13912326.25
#Sta/Elev= 30
  4669.6 1921.51  4750.7 1908.42  4786.5 1905.45  4801.3  1901.6  4822.3 1899.87
  4837.1 1895.62  4866.1 1891.86    4873 1890.36    4879 1885.72  4887.8 1882.11
  4893.9  1873.3    4900 1871.77  4941.8 1867.16  4946.8 1868.98  4963.5 1863.61
  4983.8 1860.48  5022.4 1859.65  5022.6 1859.15  5026.4 1859.65  5054.8 1860.85
  5107.9 1868.09  5112.4 1870.96  5133.5 1876.01  5148.7 1883.38  5169.8    1887
  5176.6 1890.86    5206  1893.1  5221.2 1897.86  5314.7  1905.7  5395.9 1910.46
#Mann= 3 ,-1 , 0
  4669.6     .07       0  5022.4     .05       0  5026.4     .07       0
Bank Sta=5022.4,5026.4
XS Rating Curve= 0 ,0
Exp/Cntr=0.3,0.1

Chan Stop Cuts=-1
Use User Specified Reach Order=0
Composite Channel Slope=5