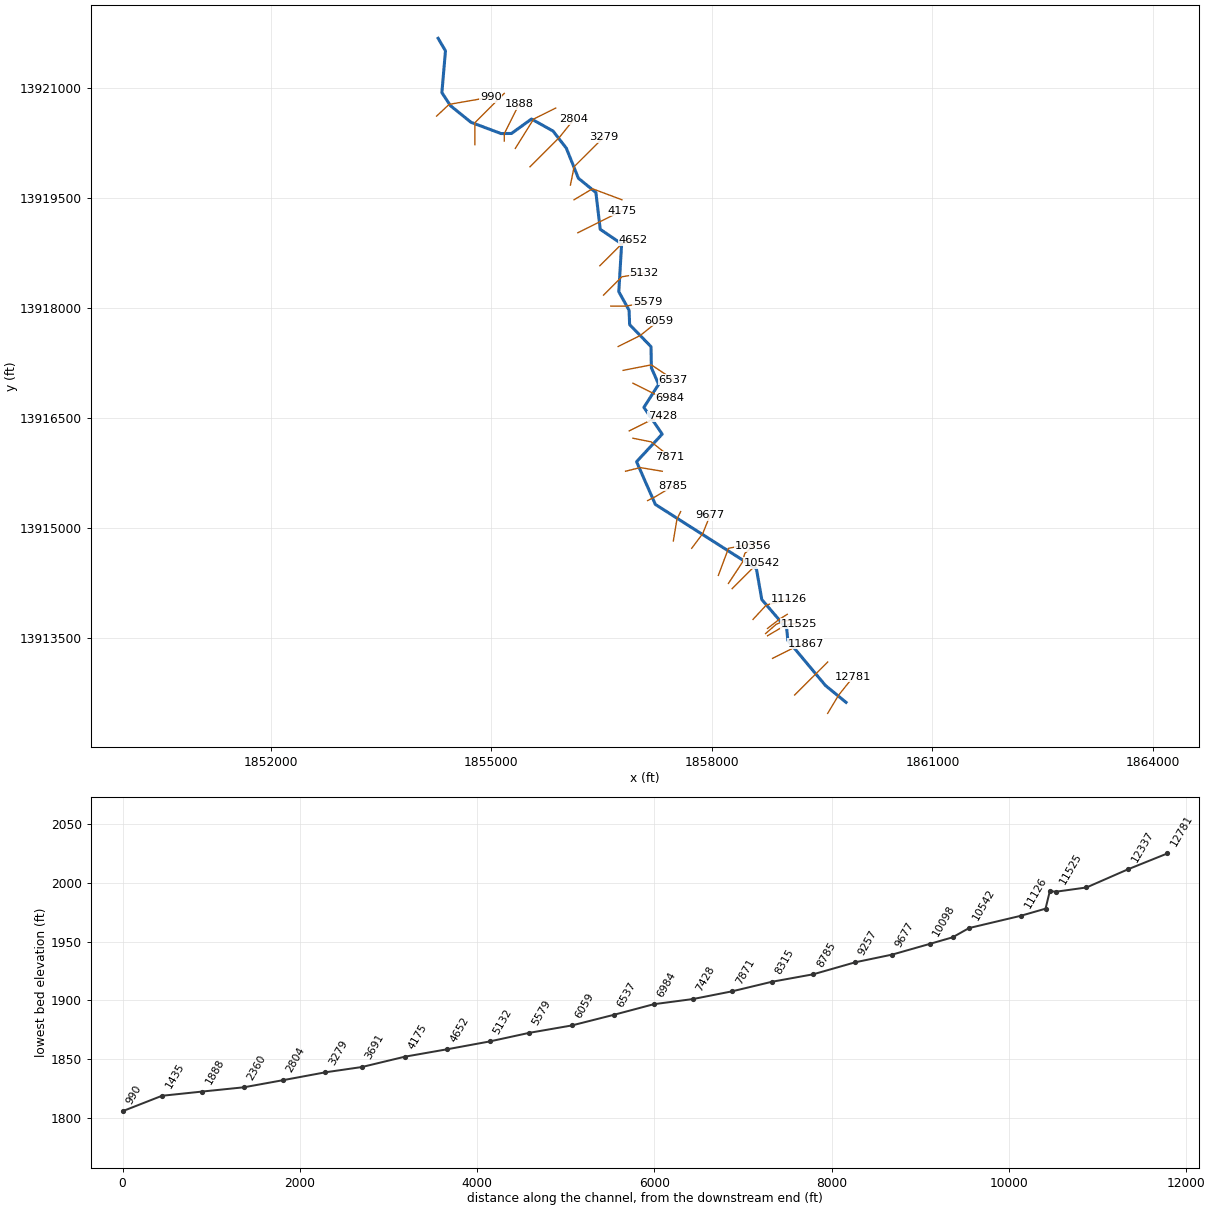
--- Stream0303.prj (project) ---

Proj Title=Stream0303 Base Level Engineering
Current Plan=p01
Default Exp/Contr=0.3,0.1
English Units
Geom File=g01
Flow File=f01
Plan File=p01
BEGIN DESCRIPTION:
Stream0303
END DESCRIPTION:

--- Stream0303.p01 (plan) ---

Plan Title=Multiple Run
Short Identifier=Multiple
Geom File=g01
Flow File=f01
Subcritical Flow
K Sum by GR= 0
Std Step Tol= 0.01
Critical Tol= 0.01
Num of Std Step Trials= 20
Max Error Tol= 0.3
Flow Tol Ratio= 0.001
Split Flow NTrial= 30
Split Flow Tol= 0.02
Split Flow Ratio= 0.02
Log Output Level= 0
Friction Slope Method= 1
Unsteady Friction Slope Method= 2
Unsteady Bridges Friction Slope Method= 1
Parabolic Critical Depth
Global Vel Dist=  1 , 1 , 1
Global Log Level= 0
CheckData=True
Encroach Param= -1, 0, 0, 0
BEGIN DESCRIPTION:
Multiple Run
END DESCRIPTION:

--- Stream0303.f01 (steady flow) ---

Flow Title=Multiple
Number of Profiles=7
Profile Names=10-year,25-year,50-year,1pct_min,100-year,1pct_plu,500-year
River Rch & RM= Stream0303,Reach-1,12781
     712    1191    1639    1094    2182    4354    3815
River Rch & RM= Stream0303,Reach-1,9677
    2037    3621    5190    3590    7163   14292   13490
River Rch & RM= Stream0303,Reach-1,3691
    2083    3714    5331    3691    7365   14695   13910
Boundary for River Rch & Prof#=Stream0303,Reach-1,1
Up Type=0
Dn Type=3
Dn Slope=0.005
Boundary for River Rch & Prof#=Stream0303,Reach-1,2
Up Type=0
Dn Type=3
Dn Slope=0.005
Boundary for River Rch & Prof#=Stream0303,Reach-1,3
Up Type=0
Dn Type=3
Dn Slope=0.005
Boundary for River Rch & Prof#=Stream0303,Reach-1,4
Up Type=0
Dn Type=3
Dn Slope=0.005
Boundary for River Rch & Prof#=Stream0303,Reach-1,5
Up Type=0
Dn Type=3
Dn Slope=0.005
Boundary for River Rch & Prof#=Stream0303,Reach-1,6
Up Type=0
Dn Type=3
Dn Slope=0.005
Boundary for River Rch & Prof#=Stream0303,Reach-1,7
Up Type=0
Dn Type=3
Dn Slope=0.005

--- Stream0303.g01 (geometry) ---

Geom Title=Existing Conditions

River Reach=Stream0303,Reach-1
Reach XY= 30
      1859825.00     13912625.00      1859544.77     13912854.87
      1859032.82     13913468.81      1859017.17     13913631.19
      1858678.54     13914026.46      1858605.38     13914445.47
      1857230.52     13915322.56      1856974.70     13915904.82
      1857323.43     13916281.04      1857074.63     13916645.20
      1857274.91     13916959.60      1857176.22     13917185.50
      1857171.25     13917473.45      1856880.46     13917772.55
      1856872.93     13917969.14      1856733.08     13918221.70
      1856771.64     13918873.75      1856480.47     13919072.55
      1856421.46     13919573.54      1856183.02     13919768.66
      1856019.46     13920177.42      1855838.24     13920411.39
      1855545.16     13920575.47      1855273.44     13920378.74
      1855130.94     13920377.25      1854722.55     13920530.47
      1854441.64     13920758.29      1854326.05     13920935.44
      1854375.04     13921505.02      1854275.00     13921675.00

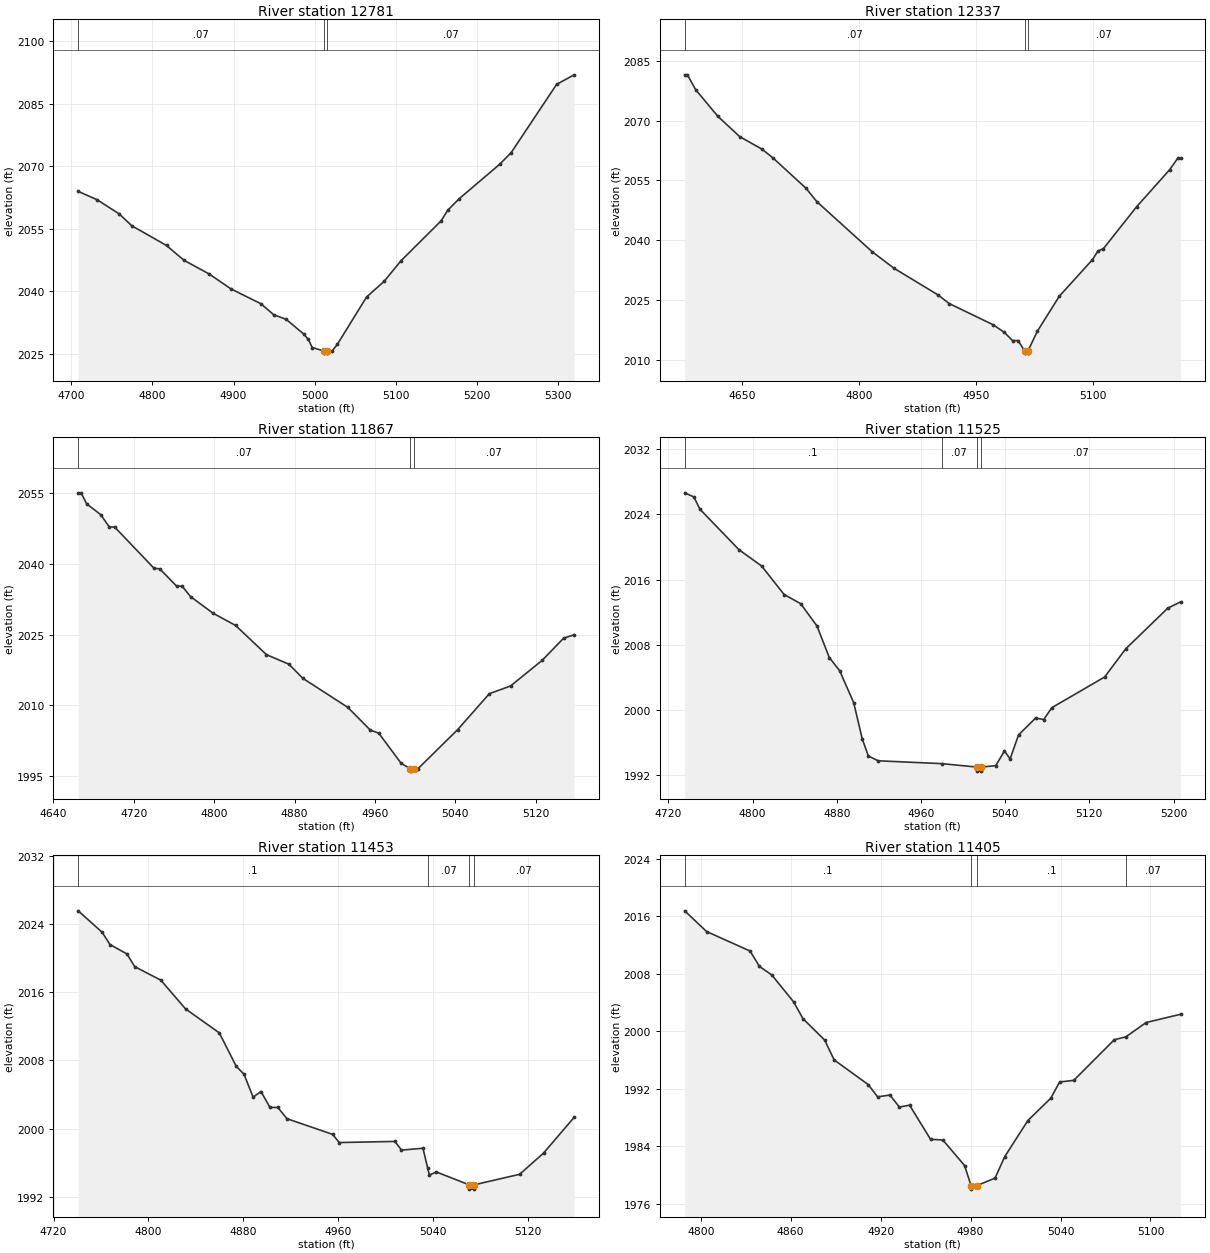
Type RM Length L Ch R = 1,12781,444,444,444
BEGIN DESCRIPTION:
Stream0303 28.0
END DESCRIPTION:
XS GIS Cut Line= 3
      1859574.98     13912474.97      1859725.00     13912725.00
      1859924.97     13912974.97
#Sta/Elev= 30
  4708.4 2063.95  4731.8 2061.93  4759.0 2058.53  4774.5 2055.69  4817.3 2050.96
  4838.7 2047.42  4869.8 2044.13  4897.0 2040.51  4933.9 2036.95  4949.5 2034.33
  4965.0 2033.21  4986.4 2029.72  4992.2 2028.40  4997.1 2026.44  5011.6 2025.61
  5011.8 2025.11  5015.3 2025.11  5015.6 2025.61  5021.6 2025.61  5028.0 2027.21
  5064.0 2038.57  5085.6 2042.32  5106.4 2047.26  5156.1 2056.89  5164.1 2059.41
  5178.5 2062.22  5228.1 2070.43  5242.5 2073.27  5298.5 2089.65  5320.1 2091.93
#Mann=3,-1,0
  4708.4    0.07       0  5011.6    0.05       0  5015.6    0.07       0
Bank Sta=5011.6,5015.6
Exp/Cntr=0.3,0.1

Type RM Length L Ch R = 1,12337,470,470,470
BEGIN DESCRIPTION:
Stream0303 27.0
END DESCRIPTION:
XS GIS Cut Line= 3
      1859125.03     13912725.03      1859425.00     13913025.00
      1859575.03     13913175.03
#Sta/Elev= 30
  4576.0 2081.47  4579.5 2081.47  4590.1 2077.75  4618.4 2071.09  4646.7 2065.95
  4675.0 2062.84  4689.1 2060.65  4731.5 2053.04  4745.7 2049.62  4816.4 2037.10
  4844.7 2032.91  4901.2 2026.22  4915.4 2024.07  4971.9 2018.73  4986.1 2016.84
  4996.7 2014.78  5003.8 2014.78  5012.4 2012.12  5012.6 2011.62  5016.1 2011.62
  5016.4 2012.12  5028.5 2017.10  5056.8 2025.92  5099.2 2035.06  5106.3 2037.23
  5113.4 2037.86  5155.8 2048.33  5198.2 2057.63  5208.8 2060.55  5212.4 2060.55
#Mann=3,-1,0
  4576.0    0.07       0  5012.4    0.05       0  5016.4    0.07       0
Bank Sta=5012.4,5016.4
Exp/Cntr=0.3,0.1

Type RM Length L Ch R = 1,11867,342,342,342
BEGIN DESCRIPTION:
Stream0303 26.0
END DESCRIPTION:
XS GIS Cut Line= 3
      1858824.97     13913224.99      1859125.00     13913375.00
      1859275.04     13913425.01
#Sta/Elev= 30
  4664.6 2055.05  4667.4 2055.05  4673.0 2052.72  4687.0 2050.43  4695.4 2047.86
  4701.0 2047.77  4740.1 2039.05  4745.7 2038.95  4762.5 2035.29  4768.0 2035.27
  4776.4 2033.07  4798.8 2029.54  4821.2 2026.96  4851.9 2020.77  4874.3 2018.74
  4888.2 2015.74  4933.0 2009.58  4955.3 2004.78  4963.7 2004.13  4986.1 1997.72
  4995.2 1996.58  4995.5 1996.08  4999.2 1996.58  5002.7 1996.58  5042.2 2004.86
  5073.8 2012.49  5094.9 2014.12  5126.5 2019.58  5147.6 2024.23  5158.2 2024.98
#Mann=3,-1,0
  4664.6    0.07       0  4995.2    0.05       0  4999.2    0.07       0
Bank Sta=4995.2,4999.2
Exp/Cntr=0.3,0.1

Type RM Length L Ch R = 1,11525,72,72,72
BEGIN DESCRIPTION:
Stream0303 25.1
END DESCRIPTION:
XS GIS Cut Line= 4
      1858756.73     13913533.07      1858964.17     13913655.50
      1859057.17     13913692.82      1859187.19     13913697.81
#Sta/Elev= 30
  4735.5 2026.64  4744.2 2026.14  4750.0 2024.63  4787.1 2019.66  4808.6 2017.66
  4830.0 2014.16  4845.7 2013.04  4861.2 2010.30  4872.9 2006.43  4882.7 2004.82
  4896.1 2000.89  4904.2 1996.45  4910.0 1994.35  4919.3 1993.76  4979.7 1993.41
  5013.1 1992.99  5013.4 1992.49  5016.9 1992.49  5017.1 1992.99  5031.1 1993.16
  5039.3 1994.97  5044.7 1993.99  5052.7 1996.93  5068.9 1999.00  5076.6 1998.82
  5084.4 2000.28  5134.5 2004.04  5154.5 2007.49  5194.5 2012.49  5206.7 2013.26
#Mann=4,-1,0
  4735.5     0.1       0  4979.7    0.07       0  5013.1    0.05       0
  5017.1    0.07       0
Bank Sta=5013.1,5017.1
Exp/Cntr=0.3,0.1

Type RM Length L Ch R = 1,11453,48,48,48
BEGIN DESCRIPTION:
Stream0303 25.2
END DESCRIPTION:
XS GIS Cut Line= 4
      1858729.58     13913562.53      1858876.07     13913689.49
      1858971.55     13913730.72      1859090.49     13913749.10
#Sta/Elev= 30
  4740.8 2025.57  4761.0 2023.05  4767.6 2021.61  4781.9 2020.51  4788.5 2019.01
  4810.4 2017.44  4831.3 2014.06  4859.8 2011.24  4874.0 2007.33  4880.6 2006.39
  4888.3 2003.70  4894.9 2004.36  4902.5 2002.49  4909.1 2002.49  4916.8 2001.17
  4955.3 1999.33  4960.9 1998.37  5007.9 1998.50  5013.4 1997.48  5031.5 1997.70
  5035.5 1995.37  5036.9 1994.56  5042.9 1994.91  5070.5 1993.40  5070.7 1992.90
  5074.2 1992.90  5074.5 1993.40  5113.0 1994.64  5133.2 1997.13  5159.0 2001.33
#Mann=4,-1,0
  4740.8     0.1       0  5035.5    0.07       0  5070.5    0.05       0
  5074.5    0.07       0
Bank Sta=5070.5,5074.5
Exp/Cntr=0.3,0.1

Type RM Length L Ch R = 1,11405,279,279,279
BEGIN DESCRIPTION:
Stream0303 25.0
END DESCRIPTION:
XS GIS Cut Line= 3
      1858756.25     13913632.79      1858920.29     13913759.31
      1859025.03     13913825.02
#Sta/Elev= 30
  4789.3 2016.74  4803.9 2013.86  4832.9 2011.15  4839.2 2009.00  4847.4 2007.82
  4861.9 2004.09  4868.2 2001.74  4882.7 1998.75  4889.0 1996.00  4911.7 1992.57
  4918.0 1990.86  4926.2 1991.11  4932.5 1989.44  4939.3 1989.70  4953.3 1984.95
  4961.5 1984.86  4976.0 1981.30  4980.3 1978.52  4980.6 1978.02  4984.3 1978.52
  4996.3 1979.55  5002.8 1982.55  5018.2 1987.56  5033.5 1990.67  5039.4 1992.93
  5048.8 1993.15  5075.9 1998.81  5083.6 1999.21  5097.1 2001.20  5120.1 2002.35
#Mann=4,-1,0
  4789.3     0.1       0  4980.3    0.05       0  4984.3     0.1       0
  5083.6    0.07       0
Bank Sta=4980.3,4984.3
Exp/Cntr=0.3,0.1

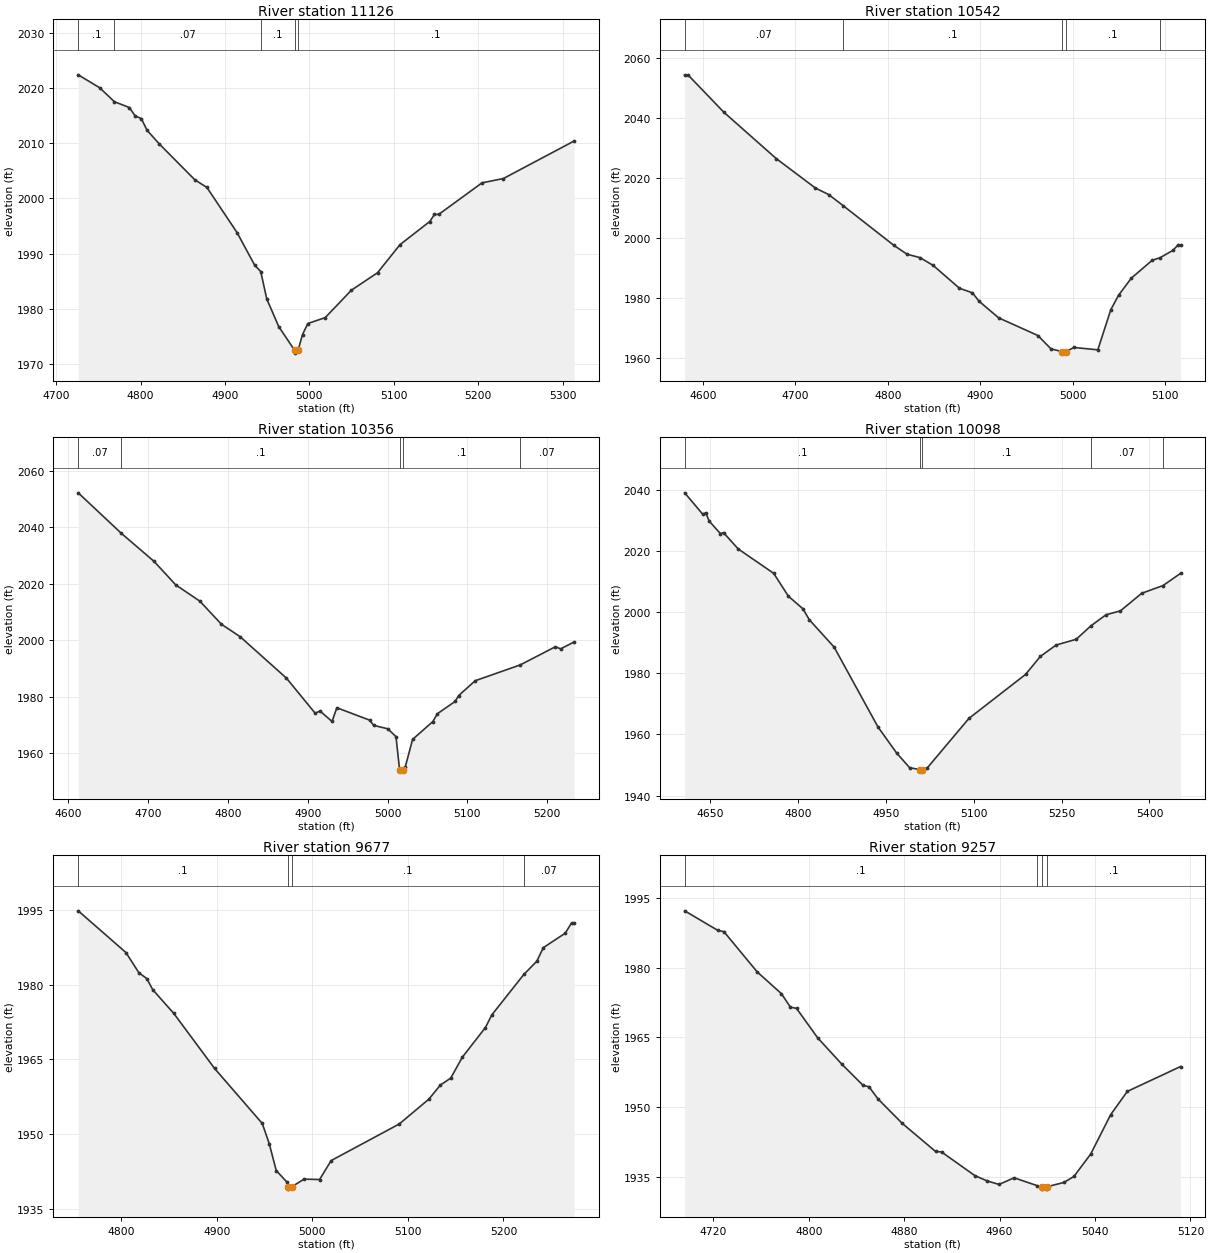
Type RM Length L Ch R = 1,11126,584,584,584
BEGIN DESCRIPTION:
Stream0303 24.0
END DESCRIPTION:
XS GIS Cut Line= 3
      1858558.84     13913755.46      1858739.91     13913951.46
      1859050.79     13914030.87
#Sta/Elev= 30
  4726.1 2022.42  4751.6 2020.07  4768.9 2017.55  4786.7 2016.49  4793.6 2014.97
  4800.9 2014.48  4807.7 2012.36  4821.9 2009.93  4864.4 2003.37  4878.6 2002.00
  4914.3 1993.82  4935.3 1987.88  4942.4 1986.75  4949.5 1981.79  4963.7 1976.77
  4982.6 1972.45  4982.9 1971.95  4986.6 1972.45  4991.9 1975.32  4998.2 1977.32
  5018.8 1978.39  5049.8 1983.36  5080.8 1986.53  5107.4 1991.62  5142.7 1995.82
  5148.3 1997.10  5153.4 1997.12  5204.6 2002.83  5229.9 2003.61  5313.8 2010.42
#Mann=5,-1,0
  4726.1     0.1       0  4768.9    0.07       0  4942.4     0.1       0
  4982.6    0.05       0  4986.6     0.1       0
Bank Sta=4982.6,4986.6
Exp/Cntr=0.3,0.1

Type RM Length L Ch R = 1,10542,186,186,186
BEGIN DESCRIPTION:
Stream0303 23.0
END DESCRIPTION:
XS GIS Cut Line= 3
      1858275.01     13914175.01      1858575.00     13914475.00
      1858675.04     13914525.02
#Sta/Elev= 30
  4580.4 2054.35  4583.9 2054.35  4622.8 2041.86  4679.4 2026.40  4721.8 2016.56
  4736.0 2014.42  4752.0 2010.63  4806.7 1997.42  4820.8 1994.50  4834.9 1993.35
  4849.1 1990.74  4877.4 1983.15  4891.5 1981.61  4898.6 1978.81  4919.8 1973.27
  4962.2 1967.38  4976.4 1962.91  4988.5 1962.00  4988.8 1961.50  4992.5 1962.00
  5001.1 1963.39  5027.0 1962.60  5041.0 1975.96  5049.4 1980.81  5063.3 1986.54
  5085.7 1992.46  5094.6 1993.38  5108.1 1995.78  5113.7 1997.56  5116.5 1997.56
#Mann=5,-1,0
  4580.4    0.07       0  4752.0     0.1       0  4988.5    0.05       0
  4992.5     0.1       0  5094.6    0.07       0
Bank Sta=4988.5,4992.5
Exp/Cntr=0.3,0.1

Type RM Length L Ch R = 1,10356,258,258,258
BEGIN DESCRIPTION:
Mapping XS 5a0cb6bc
END DESCRIPTION:
XS GIS Cut Line= 4
      1858224.29     13914245.58      1858413.54     13914532.61
      1858447.59     13914656.32      1858562.76     13914751.14
#Sta/Elev= 30
  4612.4 2052.19  4666.2 2037.90  4707.5 2027.88  4734.6 2019.57  4764.8 2013.81
  4791.8 2005.64  4815.3 2001.21  4873.2 1986.56  4909.3 1974.10  4915.3 1974.91
  4930.4 1971.19  4936.4 1976.05  4977.4 1971.67  4982.6 1969.80  5000.2 1968.60
  5010.5 1965.82  5015.0 1954.10  5015.2 1953.60  5019.0 1954.10  5022.2 1955.15
  5031.3 1964.84  5056.6 1971.14  5062.4 1973.93  5084.5 1978.28  5089.0 1980.37
  5109.8 1985.63  5166.0 1991.21  5210.2 1997.66  5216.7 1996.91  5233.7 1999.35
#Mann=5,-1,0
  4612.4    0.07       0  4666.2     0.1       0  5015.0    0.05       0
  5019.0     0.1       0  5166.0    0.07       0
Bank Sta=5015,5019
Exp/Cntr=0.3,0.1

Type RM Length L Ch R = 1,10098,421,421,421
BEGIN DESCRIPTION:
Stream0303 22.0
END DESCRIPTION:
XS GIS Cut Line= 3
      1858087.67     13914355.60      1858225.00     13914725.00
      1858670.29     13914809.31
#Sta/Elev= 30
  4605.9 2038.96  4636.6 2032.00  4641.9 2032.43  4647.9 2029.70  4667.0 2025.61
  4672.3 2025.95  4697.3 2020.62  4758.0 2012.64  4783.0 2005.18  4808.0 2001.04
  4818.7 1997.50  4861.3 1988.50  4936.0 1962.47  4968.0 1953.90  4990.2 1949.10
  5008.2 1948.48  5008.4 1947.98  5012.2 1948.48  5020.4 1949.04  5091.6 1965.23
  5188.2 1979.58  5213.7 1985.50  5240.5 1989.20  5274.8 1991.08  5299.8 1995.45
  5325.7 1999.09  5350.3 2000.37  5386.8 2006.12  5423.2 2008.65  5453.2 2012.65
#Mann=5,-1,0
  4605.9     0.1       0  5008.2    0.05       0  5012.2     0.1       0
  5299.8    0.07       0  5423.2     0.1       0
Bank Sta=5008.2,5012.2
Exp/Cntr=0.3,0.1

Type RM Length L Ch R = 1,9677,420,420,420
BEGIN DESCRIPTION:
Stream0303 21.0
END DESCRIPTION:
XS GIS Cut Line= 3
      1857725.02     13914725.03      1857875.00     13914925.00
      1857974.99     13915174.98
#Sta/Elev= 30
  4754.8 1994.88  4804.8 1986.49  4818.3 1982.43  4826.6 1981.26  4832.9 1979.00
  4854.8 1974.27  4897.5 1963.20  4947.5 1952.12  4954.8 1948.05  4962.1 1942.66
  4973.5 1940.29  4974.6 1939.42  4974.9 1938.92  4978.6 1939.42  4991.2 1940.93
  5007.5 1940.85  5019.6 1944.66  5090.9 1952.02  5121.9 1957.01  5134.0 1959.86
  5144.8 1961.24  5156.9 1965.44  5181.1 1971.41  5187.9 1973.98  5221.3 1982.08
  5235.0 1984.77  5241.7 1987.47  5264.6 1990.37  5271.3 1992.44  5274.0 1992.44
#Mann=4,-1,0
  4754.8     0.1       0  4974.6    0.05       0  4978.6     0.1       0
  5221.3    0.07       0
Bank Sta=4974.6,4978.6
Exp/Cntr=0.3,0.1

Type RM Length L Ch R = 1,9257,472,472,472
BEGIN DESCRIPTION:
Stream0303 20.0
END DESCRIPTION:
XS GIS Cut Line= 3
      1857475.00     13914825.00      1857525.00     13915125.00
      1857574.98     13915224.97
#Sta/Elev= 30
  4695.9 1992.25  4723.8 1988.02  4728.8 1987.77  4756.7 1979.10  4777.0 1974.41
  4784.6 1971.50  4789.7 1971.24  4807.4 1964.90  4827.7 1959.22  4845.4 1954.68
  4850.5 1954.35  4858.1 1951.71  4878.4 1946.46  4906.3 1940.42  4911.3 1940.32
  4939.2 1935.23  4949.3 1934.10  4959.5 1933.32  4972.2 1934.75  4991.5 1933.06
  4995.5 1932.81  4995.7 1932.31  4999.2 1932.31  4999.5 1932.81  5014.0 1933.75
  5022.4 1935.06  5036.4 1939.87  5053.1 1948.33  5067.1 1953.36  5111.8 1958.72
#Mann=4,-1,0
  4695.9     0.1       0  4991.5    0.07       0  4995.5    0.05       0
  4999.5     0.1       0
Bank Sta=4995.5,4999.5
Exp/Cntr=0.3,0.1

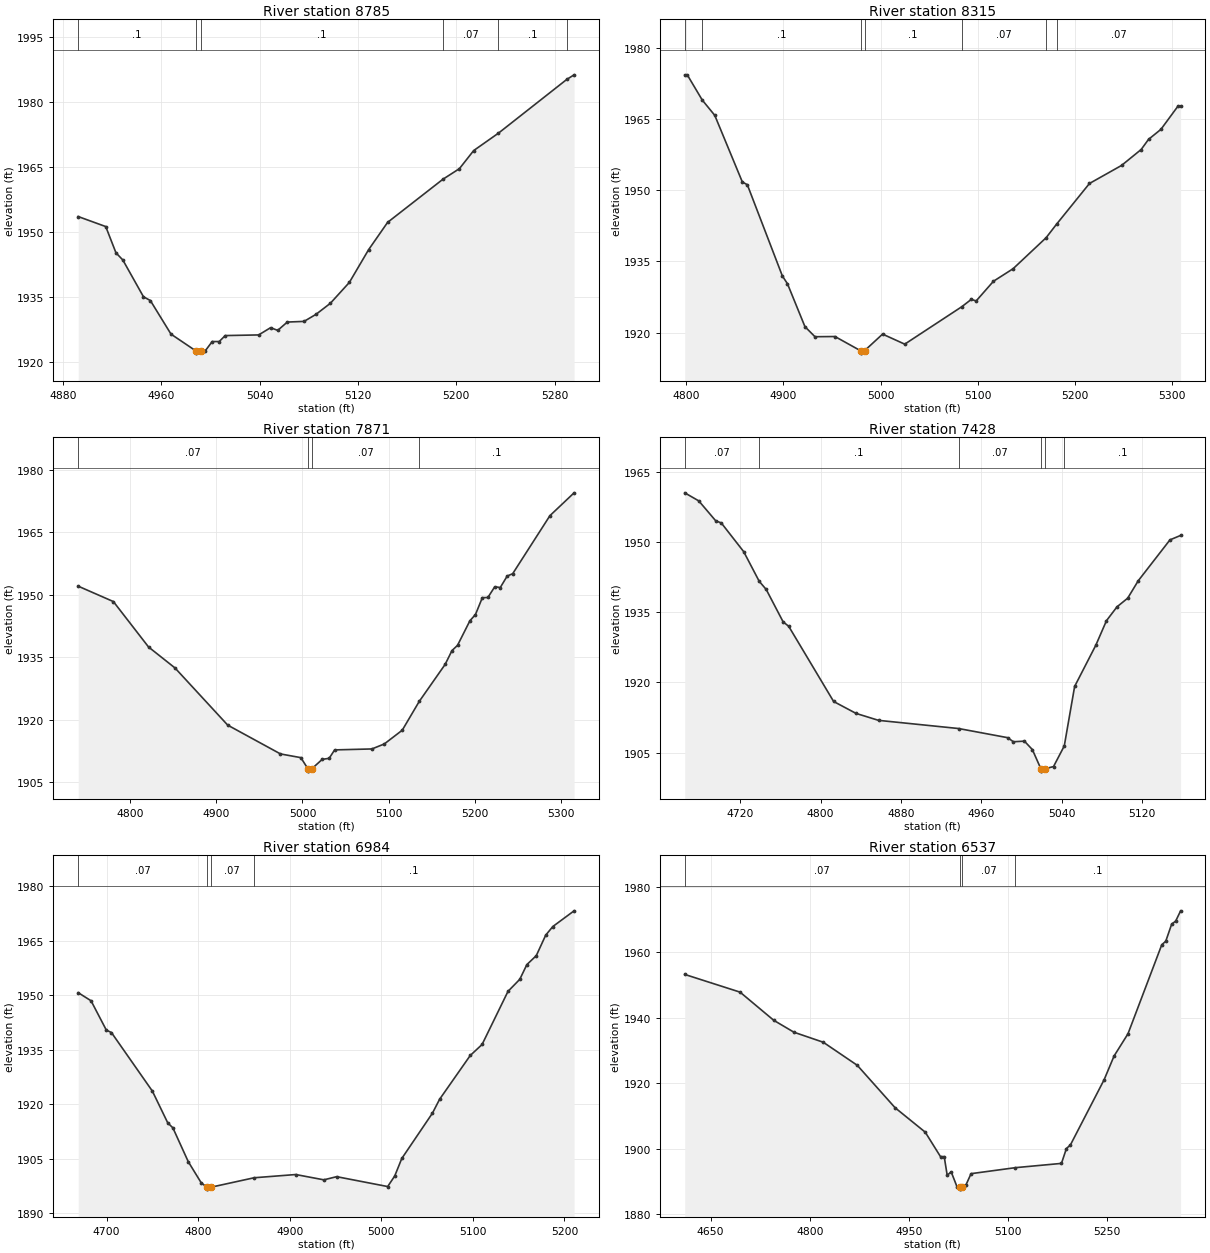
Type RM Length L Ch R = 1,8785,470,470,470
BEGIN DESCRIPTION:
Stream0303 19.0
END DESCRIPTION:
XS GIS Cut Line= 3
      1857125.00     13915375.00      1857225.00     13915425.00
      1857475.04     13915575.02
#Sta/Elev= 30
  4892.4 1953.63  4914.8 1951.32  4923.1 1945.27  4928.7 1943.61  4945.5 1935.12
  4951.1 1934.25  4967.9 1926.50  4988.2 1922.62  4988.5 1922.12  4992.2 1922.62
  4995.8 1922.67  5001.4 1924.79  5007.1 1924.79  5012.0 1926.17  5039.2 1926.32
  5048.9 1927.99  5054.7 1927.37  5062.5 1929.29  5076.1 1929.44  5085.8 1931.06
  5097.5 1933.61  5113.0 1938.44  5128.6 1945.97  5144.1 1952.29  5189.1 1962.24
  5202.5 1964.68  5214.1 1968.85  5234.3 1972.88  5289.8 1985.26  5295.8 1986.33
#Mann=6,-1,0
  4892.4     0.1       0  4988.2    0.05       0  4992.2     0.1       0
  5189.1    0.07       0  5234.3     0.1       0  5289.8    0.07       0
Bank Sta=4988.2,4992.2
Exp/Cntr=0.3,0.1

Type RM Length L Ch R = 1,8315,444,444,444
BEGIN DESCRIPTION:
Stream0303 18.0
END DESCRIPTION:
XS GIS Cut Line= 3
      1856825.00     13915775.00      1857025.00     13915825.00
      1857325.01     13915775.00
#Sta/Elev= 30
  4798.5 1974.34  4801.1 1974.34  4816.5 1969.03  4829.4 1965.80  4857.8 1951.74
  4862.9 1951.18  4899.0 1931.93  4904.2 1930.31  4922.2 1921.26  4932.5 1919.14
  4953.1 1919.18  4979.5 1916.18  4979.7 1915.68  4983.5 1916.18  5002.1 1919.69
  5024.9 1917.57  5083.6 1925.46  5093.4 1927.01  5098.4 1926.68  5116.2 1930.83
  5136.4 1933.47  5170.4 1940.01  5181.1 1942.85  5215.0 1951.44  5248.0 1955.24
  5268.2 1958.60  5275.8 1960.74  5288.5 1962.84  5306.3 1967.80  5308.8 1967.80
#Mann=7,-1,0
  4798.5    0.07       0  4816.5     0.1       0  4979.5    0.05       0
  4983.5     0.1       0  5083.6    0.07       0  5170.4     0.1       0
  5181.1    0.07       0
Bank Sta=4979.5,4983.5
Exp/Cntr=0.3,0.1

Type RM Length L Ch R = 1,7871,443,443,443
BEGIN DESCRIPTION:
Stream0303 17.0
END DESCRIPTION:
XS GIS Cut Line= 3
      1856924.98     13916225.00      1857175.00     13916175.00
      1857424.98     13915975.02
#Sta/Elev= 30
  4739.9 1952.06  4780.7 1948.36  4821.5 1937.44  4852.1 1932.42  4913.3 1918.67
  4974.5 1911.75  4998.1 1910.86  5006.5 1908.12  5006.7 1907.62  5010.5 1908.12
  5022.9 1910.45  5030.9 1910.69  5037.3 1912.72  5080.5 1912.95  5094.9 1914.15
  5115.7 1917.45  5135.4 1924.37  5165.4 1933.25  5173.4 1936.59  5179.8 1937.84
  5194.2 1943.76  5200.6 1945.24  5208.6 1949.30  5215.0 1949.34  5223.0 1951.92
  5229.4 1951.74  5237.4 1954.49  5243.8 1955.06  5287.0 1969.01  5315.0 1974.49
#Mann=4,-1,0
  4739.9    0.07       0  5006.5    0.05       0  5010.5    0.07       0
  5135.4     0.1       0
Bank Sta=5006.5,5010.5
Exp/Cntr=0.3,0.1

Type RM Length L Ch R = 1,7428,444,444,444
BEGIN DESCRIPTION:
Stream0303 16.0
END DESCRIPTION:
XS GIS Cut Line= 3
      1856874.97     13916324.99      1857175.00     13916475.00
      1857325.04     13916525.01
#Sta/Elev= 30
  4664.8 1960.60  4678.8 1958.87  4695.6 1954.62  4701.2 1954.15  4723.5 1948.00
  4738.9 1941.67  4745.9 1939.91  4762.7 1932.99  4768.3 1932.02  4813.0 1915.93
  4835.3 1913.38  4857.7 1911.89  4937.4 1910.14  4986.3 1908.18  4991.9 1907.31
  5002.9 1907.44  5010.8 1905.64  5019.3 1901.52  5019.6 1901.02  5023.3 1901.52
  5031.9 1902.00  5042.6 1906.42  5052.9 1919.15  5074.0 1927.98  5084.6 1933.23
  5095.1 1936.20  5105.7 1938.04  5116.2 1941.77  5147.8 1950.53  5158.4 1951.48
#Mann=6,-1,0
  4664.8    0.07       0  4738.9     0.1       0  4937.4    0.07       0
  5019.3    0.05       0  5023.3    0.07       0  5042.6     0.1       0
Bank Sta=5019.3,5023.3
Exp/Cntr=0.3,0.1

Type RM Length L Ch R = 1,6984,447,447,447
BEGIN DESCRIPTION:
Stream0303 15.0
END DESCRIPTION:
XS GIS Cut Line= 3
      1856925.01     13916975.00      1857225.00     13916825.00
      1857425.04     13916774.99
#Sta/Elev= 30
  4668.9 1950.70  4682.9 1948.48  4699.6 1940.40  4705.2 1939.72  4749.9 1923.59
  4766.7 1914.84  4772.3 1913.47  4789.1 1904.15  4803.1 1898.39  4809.4 1897.09
  4809.7 1896.59  4813.4 1897.09  4861.0 1899.72  4906.5 1900.61  4937.2 1899.15
  4951.2 1900.02  5006.9 1897.30  5014.6 1900.21  5022.3 1905.03  5055.8 1917.52
  5063.6 1921.34  5097.1 1933.41  5110.0 1936.43  5138.3 1951.06  5151.2 1954.39
  5158.9 1958.43  5169.2 1960.90  5179.5 1966.55  5187.3 1968.93  5210.5 1973.25
#Mann=4,-1,0
  4668.9    0.07       0  4809.4    0.05       0  4813.4    0.07       0
  4861.0     0.1       0
Bank Sta=4809.4,4813.4
Exp/Cntr=0.3,0.1

Type RM Length L Ch R = 1,6537,478,478,478
BEGIN DESCRIPTION:
Stream0303 14.0
END DESCRIPTION:
XS GIS Cut Line= 3
      1856792.92     13917149.91      1857175.00     13917225.00
      1857474.96     13917025.03
#Sta/Elev= 30
  4611.0 1953.28  4694.7 1947.86  4745.6 1939.25  4776.2 1935.60  4820.5 1932.54
  4871.9 1925.49  4929.1 1912.51  4974.7 1905.04  4997.8 1897.55  5003.4 1897.55
  5007.9 1891.85  5013.9 1892.92  5022.9 1888.26  5026.9 1888.12  5027.2 1887.62
  5030.9 1888.12  5036.4 1888.96  5044.0 1892.35  5110.9 1894.18  5180.7 1895.49
  5188.2 1900.04  5194.2 1901.12  5245.3 1921.11  5260.3 1928.35  5281.3 1935.13
  5332.4 1962.36  5338.4 1963.42  5347.4 1968.68  5353.4 1969.58  5360.9 1972.73
#Mann=4,-1,0
  4611.0    0.07       0  5026.9    0.05       0  5030.9    0.07       0
  5110.9     0.1       0
Bank Sta=5026.9,5030.9
Exp/Cntr=0.3,0.1

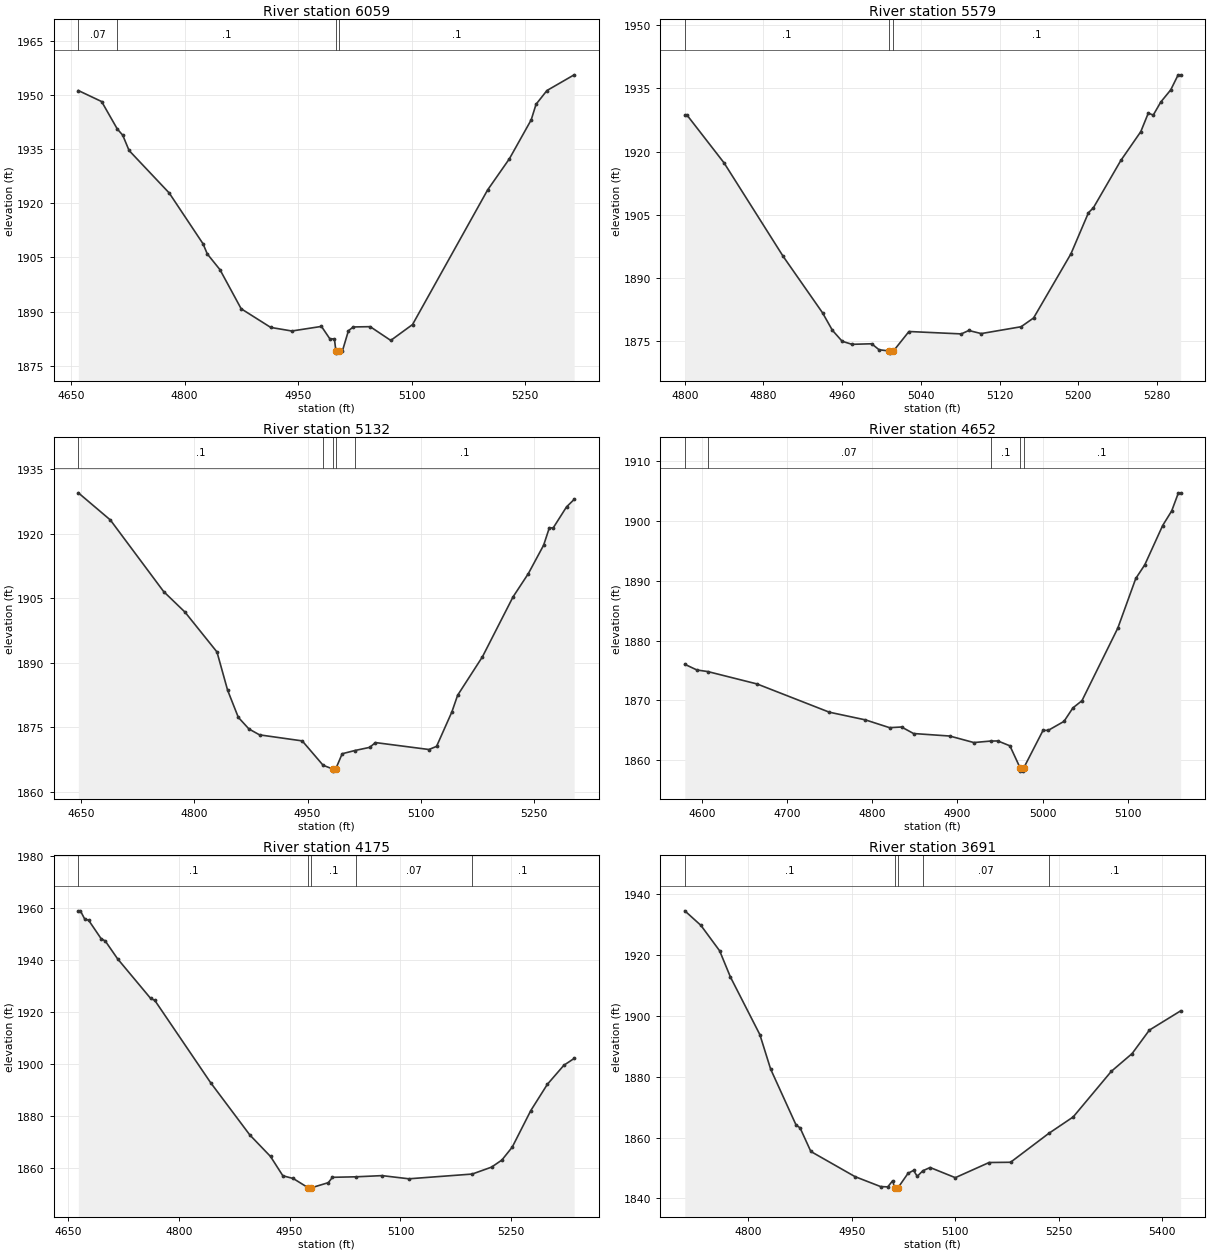
Type RM Length L Ch R = 1,6059,480,480,480
BEGIN DESCRIPTION:
Stream0303 13.0
END DESCRIPTION:
XS GIS Cut Line= 3
      1856724.97     13917474.98      1857025.00     13917625.00
      1857275.00     13917825.00
#Sta/Elev= 30
  4659.4 1951.22  4690.2 1948.17  4710.9 1940.57  4718.1 1938.85  4726.5 1934.61
  4779.6 1922.83  4824.3 1908.76  4829.9 1905.96  4846.7 1901.59  4874.7 1890.77
  4913.8 1885.60  4941.7 1884.61  4980.9 1885.88  4992.0 1882.43  4998.0 1882.43
  5000.0 1878.98  5000.3 1878.48  5004.0 1878.98  5008.5 1879.02  5016.5 1884.67
  5022.9 1885.73  5045.3 1885.81  5072.5 1882.00  5101.3 1886.40  5200.5 1923.66
  5229.4 1932.33  5258.2 1943.10  5264.6 1947.41  5279.0 1951.22  5315.0 1955.57
#Mann=4,-1,0
  4659.4    0.07       0  4710.9     0.1       0  5000.0    0.05       0
  5004.0     0.1       0
Bank Sta=5000,5004
Exp/Cntr=0.3,0.1

Type RM Length L Ch R = 1,5579,447,447,447
BEGIN DESCRIPTION:
Stream0303 12.0
END DESCRIPTION:
XS GIS Cut Line= 3
      1856625.00     13918025.00      1856825.00     13918025.00
      1857124.96     13918074.99
#Sta/Elev= 30
  4800.0 1928.59  4802.5 1928.59  4840.0 1917.30  4900.0 1895.15  4940.0 1881.77
  4950.0 1877.63  4960.0 1875.00  4970.0 1874.28  4990.0 1874.41  4997.5 1872.99
  5008.1 1872.69  5008.4 1872.19  5012.1 1872.69  5027.9 1877.32  5081.1 1876.75
  5088.7 1877.56  5101.4 1876.83  5141.9 1878.45  5154.6 1880.53  5192.6 1895.76
  5210.4 1905.51  5215.4 1906.67  5243.3 1917.90  5263.6 1924.74  5271.2 1929.12
  5276.3 1928.68  5283.9 1931.76  5294.0 1934.64  5301.6 1938.22  5304.1 1938.22
#Mann=3,-1,0
  4800.0     0.1       0  5008.1    0.05       0  5012.1     0.1       0
Bank Sta=5008.1,5012.1
Exp/Cntr=0.3,0.1

Type RM Length L Ch R = 1,5132,480,480,480
BEGIN DESCRIPTION:
Stream0303 11.0
END DESCRIPTION:
XS GIS Cut Line= 3
      1856524.98     13918174.98      1856775.00     13918425.00
      1857074.98     13918475.00
#Sta/Elev= 30
  4646.0 1929.47  4688.5 1923.16  4759.2 1906.54  4787.5 1901.77  4829.9 1892.52
  4844.0 1883.65  4858.2 1877.34  4872.3 1874.64  4886.4 1873.27  4943.0 1871.87
  4970.7 1866.21  4983.4 1865.35  4983.7 1864.85  4987.4 1865.35  4996.0 1868.89
  5012.7 1869.63  5032.5 1870.37  5040.1 1871.48  5111.1 1869.87  5121.2 1870.60
  5141.5 1878.60  5149.1 1882.46  5182.1 1891.42  5222.6 1905.30  5242.9 1910.71
  5263.2 1917.31  5270.8 1921.36  5275.8 1921.30  5293.6 1926.21  5303.7 1927.94
#Mann=5,-1,0
  4646.0     0.1       0  4970.7    0.07       0  4983.4    0.05       0
  4987.4    0.07       0  5012.7     0.1       0
Bank Sta=4983.4,4987.4
Exp/Cntr=0.3,0.1

Type RM Length L Ch R = 1,4652,477,477,477
BEGIN DESCRIPTION:
Stream0303 10.0
END DESCRIPTION:
XS GIS Cut Line= 3
      1856474.97     13918574.97      1856775.00     13918875.00
      1856924.98     13918924.99
#Sta/Elev= 30
  4579.7 1876.05  4593.9 1875.10  4606.8 1874.83  4664.6 1872.76  4749.4 1868.04
  4791.9 1866.75  4820.2 1865.45  4834.3 1865.56  4848.4 1864.47  4890.9 1864.05
  4919.2 1862.96  4939.0 1863.21  4947.4 1863.23  4961.6 1862.41  4973.7 1858.68
  4974.0 1858.18  4977.5 1858.18  4977.7 1858.68  5000.5 1865.00  5006.6 1865.00
  5025.1 1866.50  5035.6 1868.76  5046.2 1869.96  5088.3 1882.10  5109.4 1890.40
  5120.0 1892.69  5141.0 1899.26  5151.6 1901.70  5159.5 1904.73  5162.1 1904.73
#Mann=5,-1,0
  4579.7     0.1       0  4606.8    0.07       0  4939.0     0.1       0
  4973.7    0.05       0  4977.7     0.1       0
Bank Sta=4973.7,4977.7
Exp/Cntr=0.3,0.1

Type RM Length L Ch R = 1,4175,484,484,484
BEGIN DESCRIPTION:
Stream0303 9.0
END DESCRIPTION:
XS GIS Cut Line= 3
      1856174.98     13919024.99      1856475.00     13919175.00
      1856774.96     13919324.98
#Sta/Elev= 30
  4664.2 1958.80  4667.0 1958.80  4672.6 1955.76  4678.2 1955.15  4695.0 1948.11
  4700.6 1947.22  4717.3 1940.37  4762.0 1925.15  4767.6 1924.41  4843.1 1892.80
  4896.2 1872.68  4924.2 1864.41  4940.9 1856.99  4954.9 1855.95  4975.3 1852.36
  4975.5 1851.86  4979.3 1852.36  5002.4 1854.35  5008.0 1856.40  5040.4 1856.60
  5075.1 1857.05  5111.4 1855.83  5197.0 1857.65  5223.2 1860.31  5237.2 1863.03
  5251.2 1867.99  5276.3 1882.03  5298.7 1892.12  5321.1 1899.46  5335.0 1902.08
#Mann=5,-1,0
  4664.2     0.1       0  4975.3    0.05       0  4979.3     0.1       0
  5040.4    0.07       0  5197.0     0.1       0
Bank Sta=4975.3,4979.3
Exp/Cntr=0.3,0.1

Type RM Length L Ch R = 1,3691,412,412,412
BEGIN DESCRIPTION:
Stream0303 8.0
END DESCRIPTION:
XS GIS Cut Line= 3
      1856125.00     13919475.00      1856375.00     13919625.00
      1856774.96     13919475.02
#Sta/Elev= 30
  4707.8 1934.34  4731.1 1929.58  4758.3 1921.23  4773.9 1912.65  4816.6 1893.74
  4832.2 1882.45  4869.1 1864.09  4874.9 1863.16  4890.5 1855.42  4954.6 1847.16
  4991.6 1843.91  5002.0 1843.81  5009.1 1845.82  5011.9 1843.57  5012.3 1843.07
  5017.0 1843.57  5031.4 1848.26  5039.4 1849.21  5044.7 1847.27  5052.9 1849.10
  5063.4 1850.16  5099.9 1846.83  5148.9 1851.80  5180.0 1851.88  5235.2 1861.32
  5270.8 1866.75  5326.0 1881.69  5356.2 1887.53  5381.2 1895.22  5426.5 1901.53
#Mann=5,-1,0
  4707.8     0.1       0  5011.9    0.05       0  5017.0     0.1       0
  5052.9    0.07       0  5235.2     0.1       0
Bank Sta=5011.9,5017
Exp/Cntr=0.3,0.1

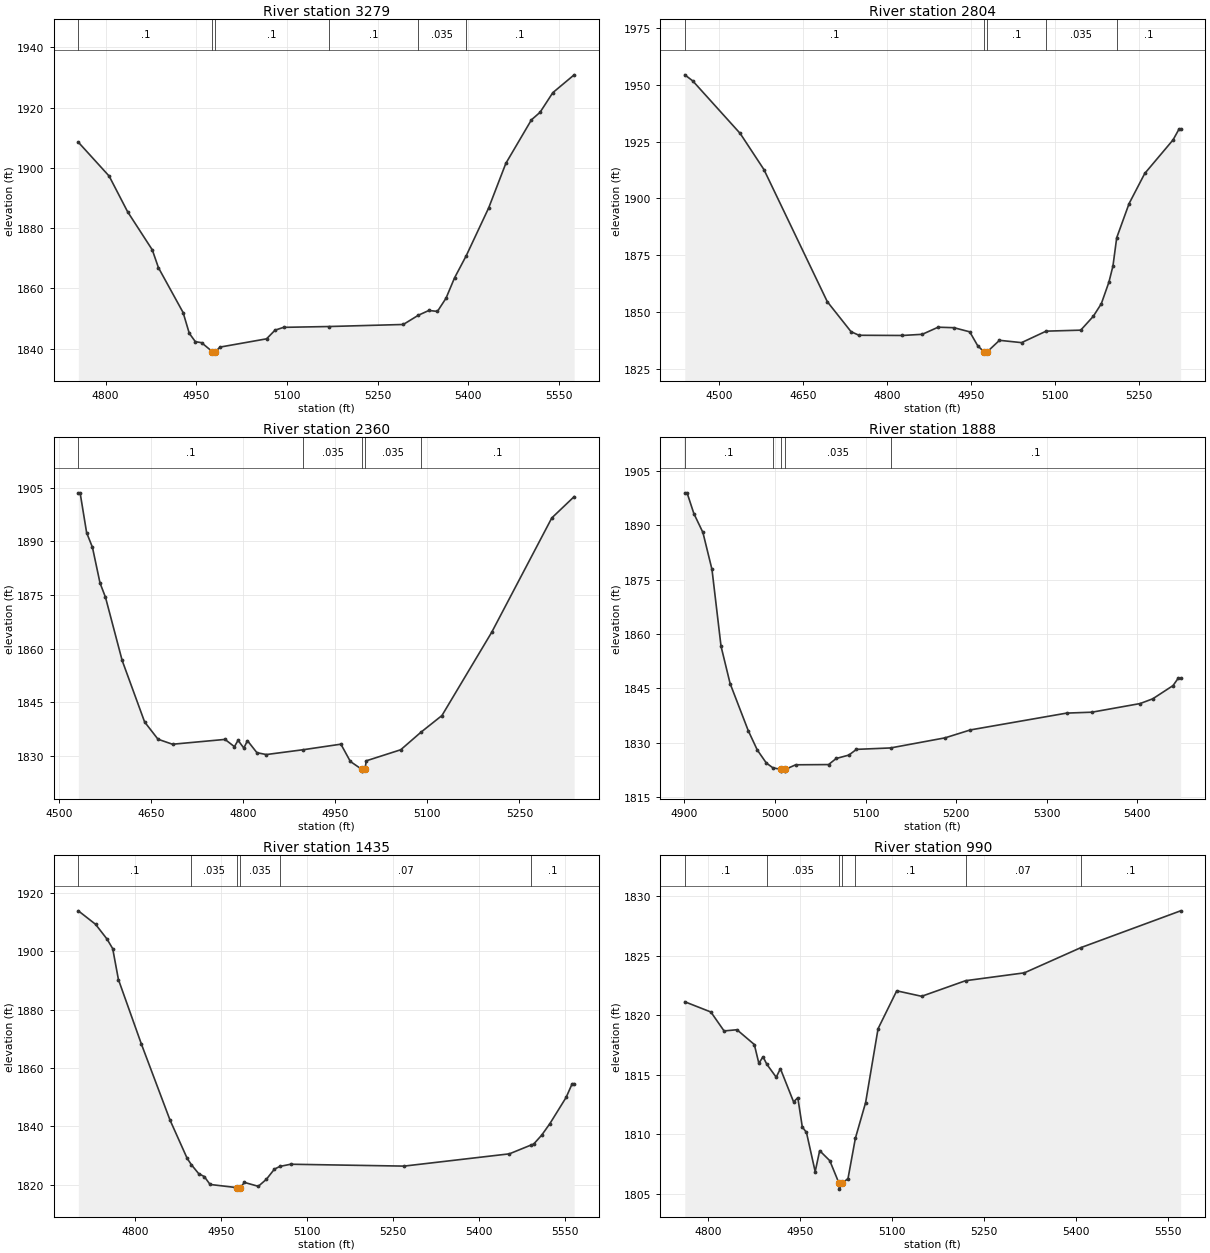
Type RM Length L Ch R = 1,3279,475,475,475
BEGIN DESCRIPTION:
Stream0303 7.0
END DESCRIPTION:
XS GIS Cut Line= 3
      1856075.00     13919675.01      1856125.00     13919925.00
      1856524.98     13920324.98
#Sta/Elev= 30
  4754.8 1908.50  4805.8 1897.26  4836.4 1885.42  4877.2 1872.80  4887.4 1866.88
  4928.2 1852.02  4938.4 1845.14  4948.5 1842.36  4958.7 1842.03  4976.6 1839.06
  4977.0 1838.56  4981.7 1839.06  4989.3 1840.56  5066.3 1843.30  5080.4 1846.18
  5094.6 1847.11  5169.4 1847.38  5292.6 1848.06  5317.6 1851.13  5335.0 1852.71
  5349.1 1852.39  5363.3 1856.76  5377.4 1863.50  5396.9 1870.90  5434.0 1886.75
  5462.3 1901.47  5504.7 1915.92  5518.9 1918.40  5540.1 1924.93  5575.4 1930.84
#Mann=6,-1,0
  4754.8     0.1       0  4976.6    0.05       0  4981.7     0.1       0
  5169.4     0.1       0  5317.6   0.035       0  5396.9     0.1       0
Bank Sta=4976.6,4981.7
Exp/Cntr=0.3,0.1

Type RM Length L Ch R = 1,2804,444,444,444
BEGIN DESCRIPTION:
Stream0303 6.0
END DESCRIPTION:
XS GIS Cut Line= 3
      1855524.99     13919924.99      1855925.00     13920325.00
      1856125.03     13920575.03
#Sta/Elev= 30
  4439.1 1954.36  4453.3 1951.69  4538.1 1928.55  4580.5 1912.67  4693.7 1854.54
  4736.1 1841.35  4750.2 1839.76  4828.0 1839.67  4863.4 1840.18  4891.7 1843.31
  4919.9 1843.09  4948.2 1841.27  4962.4 1835.17  4973.9 1832.40  4974.3 1831.90
  4979.1 1832.40  5001.3 1837.54  5040.8 1836.52  5084.7 1841.57  5146.5 1842.01
  5168.9 1848.08  5183.3 1853.64  5196.9 1863.16  5204.1 1870.25  5210.8 1882.67
  5232.9 1897.70  5260.9 1910.96  5311.4 1925.71  5321.8 1930.33  5325.0 1930.33
#Mann=5,-1,0
  4439.1     0.1       0  4973.9    0.05       0  4979.1     0.1       0
  5084.7   0.035       0  5210.8     0.1       0
Bank Sta=4973.9,4979.1
Exp/Cntr=0.3,0.1

Type RM Length L Ch R = 1,2360,472,472,472
BEGIN DESCRIPTION:
Stream0303 5.0
END DESCRIPTION:
XS GIS Cut Line= 3
      1855325.02     13920175.03      1855575.00     13920575.00
      1855875.02     13920725.01
#Sta/Elev= 30
  4531.9 1903.53  4534.8 1903.53  4545.4 1892.40  4554.9 1888.29  4567.2 1878.34
  4576.1 1874.35  4603.2 1856.73  4639.8 1839.53  4661.6 1834.71  4685.2 1833.31
  4770.7 1834.66  4786.0 1832.63  4791.9 1834.41  4801.3 1832.25  4807.2 1834.31
  4822.6 1830.95  4837.9 1830.43  4898.4 1831.79  4959.3 1833.33  4974.7 1828.50
  4993.3 1826.30  4993.7 1825.80  4998.5 1826.30  5000.6 1828.68  5056.7 1831.77
  5089.7 1836.68  5123.8 1841.33  5204.8 1864.59  5302.6 1896.52  5339.0 1902.47
#Mann=5,-1,0
  4531.9     0.1       0  4898.4   0.035       0  4993.3   0.035       0
  4998.5   0.035       0  5089.7     0.1       0
Bank Sta=4993.3,4998.5
Exp/Cntr=0.3,0.1

Type RM Length L Ch R = 1,1888,453,453,453
BEGIN DESCRIPTION:
Stream0303 4.0
END DESCRIPTION:
XS GIS Cut Line= 3
      1855175.00     13920274.96      1855175.00     13920375.00
      1855375.02     13920775.04
#Sta/Elev= 30
  4900.4 1898.98  4902.9 1898.98  4910.4 1893.26  4920.4 1888.03  4930.4 1877.83
  4940.4 1856.62  4950.4 1846.34  4970.4 1833.35  4980.4 1827.99  4990.4 1824.39
  4997.6 1823.07  5006.1 1822.65  5006.5 1822.15  5011.1 1822.15  5011.5 1822.65
  5022.8 1823.90  5059.1 1823.96  5067.5 1825.64  5081.5 1826.58  5089.9 1828.16
  5127.5 1828.55  5187.7 1831.34  5215.7 1833.53  5321.9 1838.17  5349.8 1838.42
  5402.9 1840.80  5416.9 1842.11  5439.3 1845.76  5444.9 1847.75  5447.7 1847.75
#Mann=5,-1,0
  4900.4     0.1       0  4997.6   0.035       0  5006.1   0.035       0
  5011.5   0.035       0  5127.5     0.1       0
Bank Sta=5006.1,5011.5
Exp/Cntr=0.3,0.1

Type RM Length L Ch R = 1,1435,445,445,445
BEGIN DESCRIPTION:
Stream0303 3.0
END DESCRIPTION:
XS GIS Cut Line= 3
      1854775.00     13920224.99      1854775.00     13920525.00
      1855175.00     13920925.00
#Sta/Elev= 30
  4700.3 1913.82  4730.3 1909.22  4750.3 1904.18  4760.3 1900.88  4770.3 1890.31
  4810.3 1868.27  4860.3 1842.23  4890.3 1829.10  4897.8 1826.88  4910.3 1823.89
  4920.3 1822.84  4930.3 1820.16  4977.6 1819.06  4978.0 1818.56  4983.0 1819.06
  4990.3 1820.86  5014.5 1819.52  5028.6 1821.92  5042.7 1825.41  5052.2 1826.33
  5071.0 1827.08  5269.0 1826.44  5452.9 1830.64  5490.3 1833.62  5495.3 1833.98
  5509.4 1837.06  5523.6 1840.98  5551.9 1849.93  5562.5 1854.63  5566.0 1854.63
#Mann=6,-1,0
  4700.3     0.1       0  4897.8   0.035       0  4977.6   0.035       0
  4983.0   0.035       0  5052.2    0.07       0  5490.3     0.1       0
Bank Sta=4977.6,4983
Exp/Cntr=0.3,0.1

Type RM Length L Ch R = 1,990,0,0,0
BEGIN DESCRIPTION:
Stream0303 2.0
END DESCRIPTION:
XS GIS Cut Line= 3
      1854254.26     13920615.35      1854425.00     13920775.00
      1854990.78     13920873.86
#Sta/Elev= 30
  4761.8 1821.13  4804.3 1820.27  4825.8 1818.68  4846.8 1818.78  4875.1 1817.54
  4882.5 1815.96  4889.3 1816.51  4895.5 1815.88  4910.8 1814.79  4917.6 1815.51
  4939.1 1812.72  4946.0 1813.07  4953.3 1810.61  4960.1 1810.15  4974.3 1806.86
  4981.6 1808.62  4998.1 1807.78  5013.1 1805.89  5013.5 1805.39  5018.6 1805.89
  5027.8 1806.28  5039.8 1809.66  5056.5 1812.66  5076.8 1818.87  5107.2 1822.05
  5147.8 1821.59  5219.4 1822.90  5315.2 1823.56  5407.4 1825.68  5569.9 1828.77
#Mann=7,-1,0
  4761.8     0.1       0  4895.5   0.035       0  5013.1   0.035       0
  5018.6   0.035       0  5039.8     0.1       0  5219.4    0.07       0
  5407.4     0.1       0
Bank Sta=5013.1,5018.6
Exp/Cntr=0.3,0.1

Chan Stop Cuts=-1