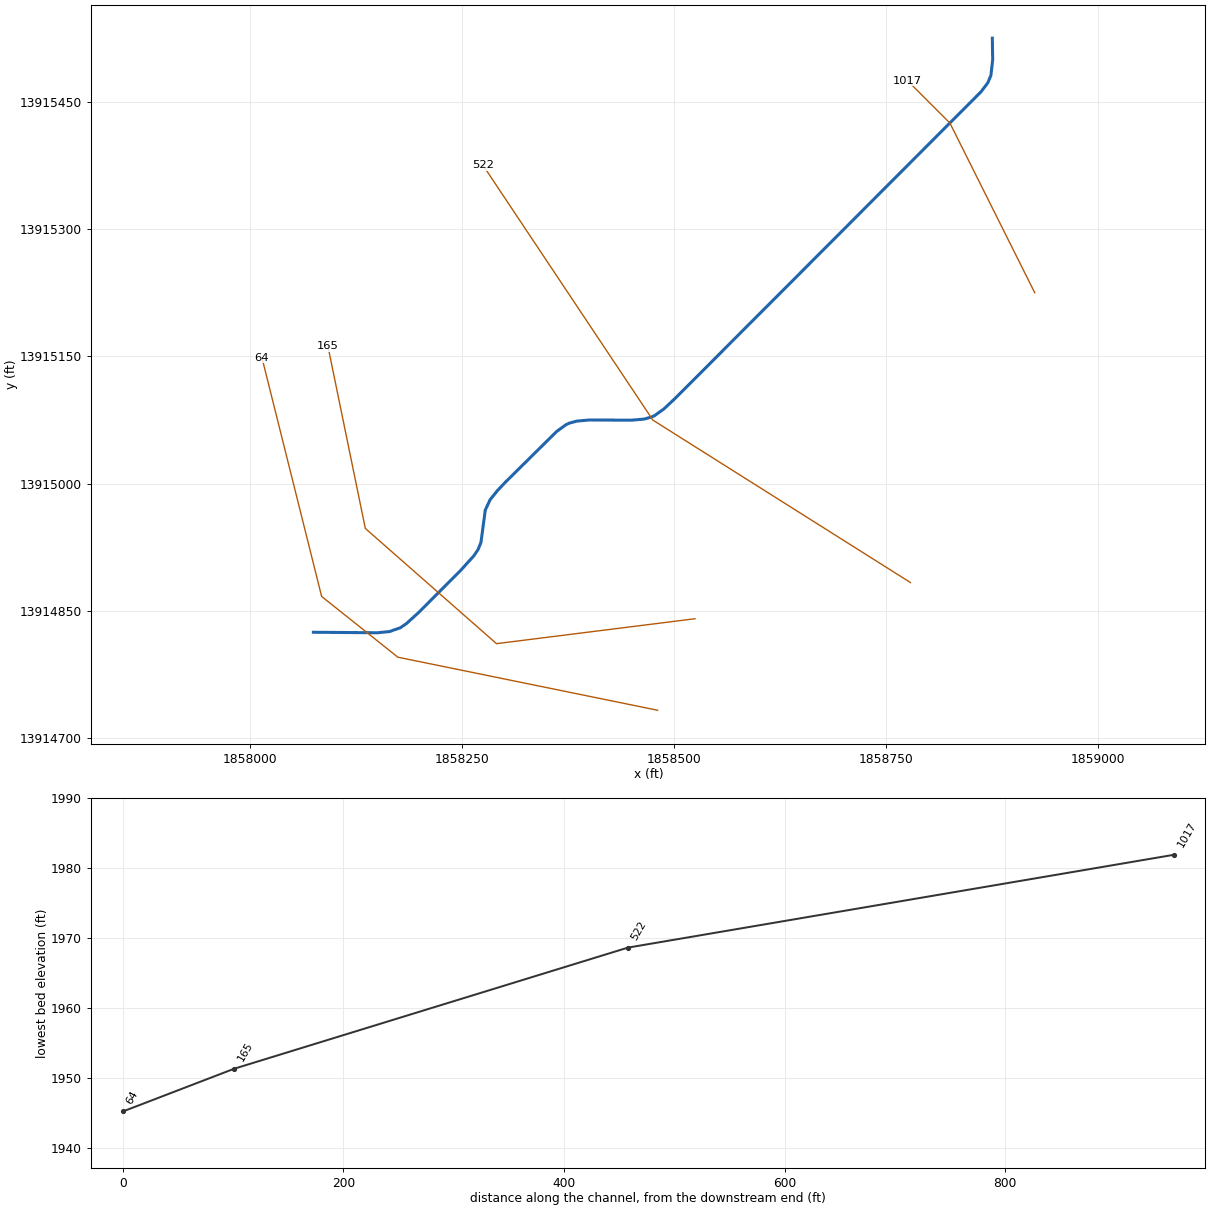
--- Stream0304.prj (project) ---

Proj Title=Stream0304 Base Level Engineering
Current Plan=p01
Default Exp/Contr=0.3,0.1
English Units
Geom File=g01
Flow File=f01
Plan File=p01
BEGIN DESCRIPTION:
Stream0304
END DESCRIPTION:

--- Stream0304.p01 (plan) ---

Plan Title=Multiple Run
Short Identifier=Multiple
Geom File=g01
Flow File=f01
Subcritical Flow
K Sum by GR= 0
Std Step Tol= 0.01
Critical Tol= 0.01
Num of Std Step Trials= 20
Max Error Tol= 0.3
Flow Tol Ratio= 0.001
Split Flow NTrial= 30
Split Flow Tol= 0.02
Split Flow Ratio= 0.02
Log Output Level= 0
Friction Slope Method= 1
Unsteady Friction Slope Method= 2
Unsteady Bridges Friction Slope Method= 1
Parabolic Critical Depth
Global Vel Dist=  1 , 1 , 1
Global Log Level= 0
CheckData=True
Encroach Param= -1, 0, 0, 0
BEGIN DESCRIPTION:
Multiple Run
END DESCRIPTION:

--- Stream0304.f01 (steady flow) ---

Flow Title=Multiple
Number of Profiles=7
Profile Names=10-year,25-year,50-year,1pct_min,100-year,1pct_plu,500-year
River Rch & RM= Stream0304,Reach-1,1017
     307     483     640     412     823    1642    1337
Boundary for River Rch & Prof#=Stream0304,Reach-1,1
Up Type=0
Dn Type=3
Dn Slope=0.005
Boundary for River Rch & Prof#=Stream0304,Reach-1,2
Up Type=0
Dn Type=3
Dn Slope=0.005
Boundary for River Rch & Prof#=Stream0304,Reach-1,3
Up Type=0
Dn Type=3
Dn Slope=0.005
Boundary for River Rch & Prof#=Stream0304,Reach-1,4
Up Type=0
Dn Type=3
Dn Slope=0.005
Boundary for River Rch & Prof#=Stream0304,Reach-1,5
Up Type=0
Dn Type=3
Dn Slope=0.005
Boundary for River Rch & Prof#=Stream0304,Reach-1,6
Up Type=0
Dn Type=3
Dn Slope=0.005
Boundary for River Rch & Prof#=Stream0304,Reach-1,7
Up Type=0
Dn Type=3
Dn Slope=0.005

--- Stream0304.g01 (geometry) ---

Geom Title=Existing Conditions

River Reach=Stream0304,Reach-1
Reach XY= 30
      1858875.00     13915525.00      1858875.41     13915499.63
      1858873.32     13915481.14      1858869.69     13915472.48
      1858861.53     13915461.73      1858501.87     13915101.18
      1858488.30     13915088.40      1858477.43     13915080.52
      1858473.50     13915078.61      1858464.52     13915076.17
      1858450.03     13915074.92      1858399.96     13915075.09
      1858385.48     13915073.84      1858376.49     13915071.39
      1858372.56     13915069.48      1858361.67     13915061.61
      1858301.27     13915001.89      1858291.64     13914991.71
      1858283.15     13914981.07      1858277.53     13914968.96
      1858272.47     13914931.04      1858269.15     13914922.70
      1858264.23     13914915.30      1858248.73     13914898.11
      1858198.57     13914847.86      1858184.84     13914835.42
      1858177.51     13914830.34      1858164.67     13914825.81
      1858150.25     13914824.40      1858075.00     13914825.00

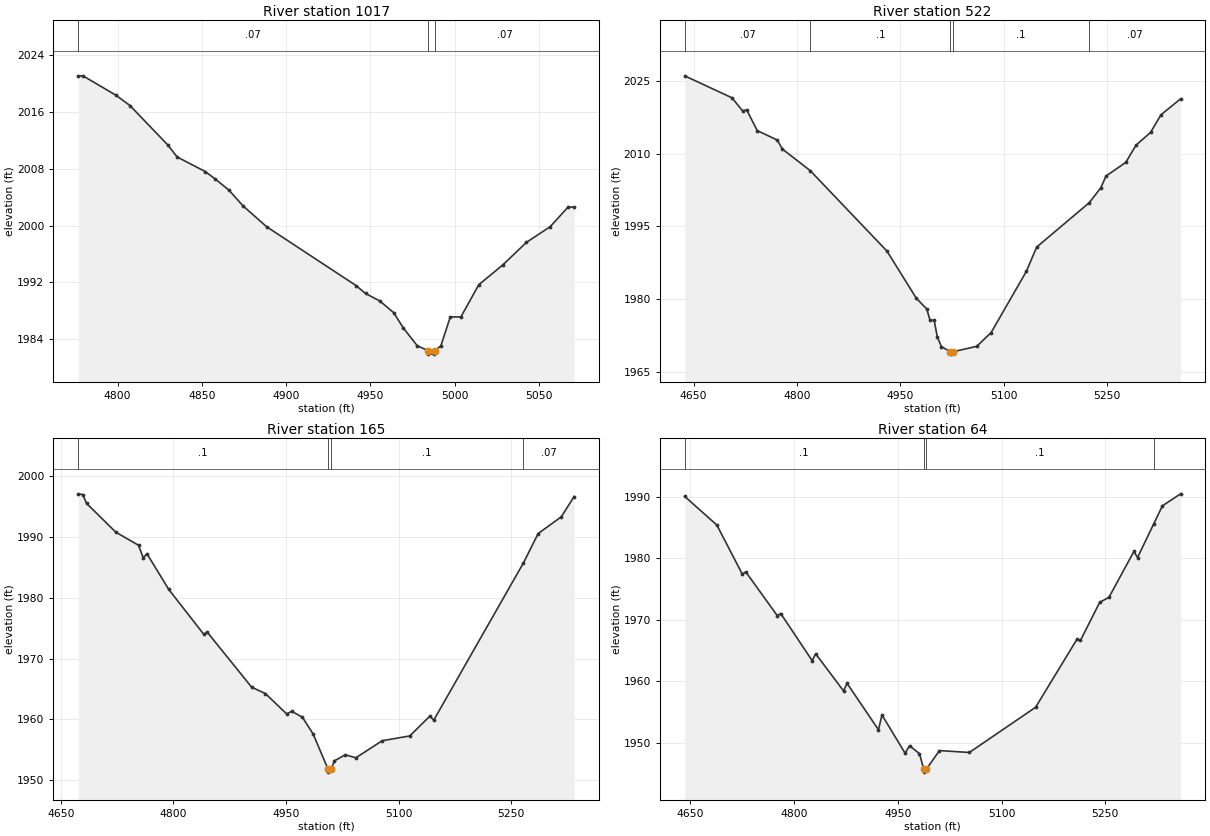
Type RM Length L Ch R = 1,1017,495,495,495
BEGIN DESCRIPTION:
Stream0304 2.0
END DESCRIPTION:
XS GIS Cut Line= 3
      1858924.98     13915225.03      1858825.00     13915425.00
      1858774.99     13915475.01
#Sta/Elev= 30
  4776.6 2021.03  4779.4 2021.03  4798.9 2018.32  4807.3 2016.86  4829.7 2011.33
  4835.3 2009.63  4852.0 2007.58  4857.6 2006.59  4866.0 2004.98  4874.4 2002.76
  4888.4 1999.83  4941.5 1991.56  4947.1 1990.45  4955.5 1989.41  4963.8 1987.76
  4969.4 1985.65  4977.8 1983.10  4984.2 1982.43  4984.4 1981.93  4987.9 1981.93
  4988.2 1982.43  4991.8 1983.09  4997.4 1987.16  5003.7 1987.16  5014.3 1991.68
  5028.5 1994.45  5042.6 1997.64  5056.7 1999.84  5067.3 2002.59  5070.9 2002.59
#Mann=3,-1,0
  4776.6    0.07       0  4984.2    0.05       0  4988.2    0.07       0
Bank Sta=4984.2,4988.2
Exp/Cntr=0.3,0.1

Type RM Length L Ch R = 1,522,357,357,357
BEGIN DESCRIPTION:
Stream0304 1.0
END DESCRIPTION:
XS GIS Cut Line= 3
      1858778.54     13914883.58      1858475.00     13915075.00
      1858275.01     13915374.99
#Sta/Elev= 30
  4637.1 2026.05  4705.8 2021.51  4721.1 2018.82  4727.0 2019.05  4742.3 2014.76
  4771.3 2012.81  4778.8 2010.95  4819.1 2006.51  4930.6 1989.89  4973.0 1980.20
  4988.3 1977.95  4993.0 1975.63  4999.0 1975.63  5003.5 1972.22  5009.5 1970.20
  5022.5 1969.15  5022.7 1968.65  5026.5 1969.15  5060.6 1970.25  5081.6 1973.09
  5132.7 1985.71  5147.7 1990.73  5224.1 1999.90  5240.8 2002.97  5248.3 2005.38
  5276.9 2008.19  5291.9 2011.76  5312.9 2014.38  5328.0 2018.01  5356.5 2021.32
#Mann=5,-1,0
  4637.1    0.07       0  4819.1     0.1       0  5022.5    0.05       0
  5026.5     0.1       0  5224.1    0.07       0
Bank Sta=5022.5,5026.5
Exp/Cntr=0.3,0.1

Type RM Length L Ch R = 1,165,101,101,101
BEGIN DESCRIPTION:
Stream0304 0.0
END DESCRIPTION:
XS GIS Cut Line= 4
      1858524.65     13914840.93      1858290.75     13914811.57
      1858136.18     13914947.32      1858092.13     13915161.89
#Sta/Elev= 30
  4673.2 1997.11  4679.3 1996.98  4684.3 1995.54  4723.2 1990.81  4753.5 1988.65
  4759.7 1986.61  4764.8 1987.24  4793.8 1981.38  4840.2 1974.03  4845.2 1974.33
  4904.3 1965.28  4922.5 1964.25  4950.9 1960.89  4957.6 1961.34  4971.8 1960.35
  4986.1 1957.59  5005.9 1951.82  5006.1 1951.32  5009.9 1951.82  5014.5 1953.18
  5028.8 1954.17  5043.0 1953.68  5078.1 1956.49  5114.7 1957.27  5141.6 1960.54
  5146.7 1959.87  5266.1 1985.73  5285.8 1990.58  5316.5 1993.32  5333.7 1996.67
#Mann=4,-1,0
  4673.2     0.1       0  5005.9    0.05       0  5009.9     0.1       0
  5266.1    0.07       0
Bank Sta=5005.9,5009.9
Exp/Cntr=0.3,0.1

Type RM Length L Ch R = 1,64,0,0,0
BEGIN DESCRIPTION:
Stream0304 0.1
END DESCRIPTION:
XS GIS Cut Line= 4
      1858480.53     13914733.11      1858174.53     13914795.61
      1858084.69     13914867.22      1858014.38     13915148.46
#Sta/Elev= 30
  4641.8 1990.10  4688.3 1985.44  4725.1 1977.45  4730.2 1977.80  4775.6 1970.70
  4780.7 1971.03  4826.1 1963.36  4831.2 1964.47  4871.5 1958.43  4876.6 1959.66
  4922.0 1952.10  4927.1 1954.51  4960.5 1948.28  4966.9 1949.50  4981.3 1948.21
  4987.4 1945.70  4987.6 1945.20  4991.4 1945.70  5010.2 1948.71  5053.4 1948.40
  5149.2 1955.76  5209.0 1966.83  5214.1 1966.65  5241.9 1972.85  5255.3 1973.67
  5291.4 1981.14  5296.6 1980.15  5320.1 1985.64  5332.6 1988.57  5358.9 1990.52
#Mann=4,-1,0
  4641.8     0.1       0  4987.4    0.05       0  4991.4     0.1       0
  5320.1    0.07       0
Bank Sta=4987.4,4991.4
Exp/Cntr=0.3,0.1

Chan Stop Cuts=-1