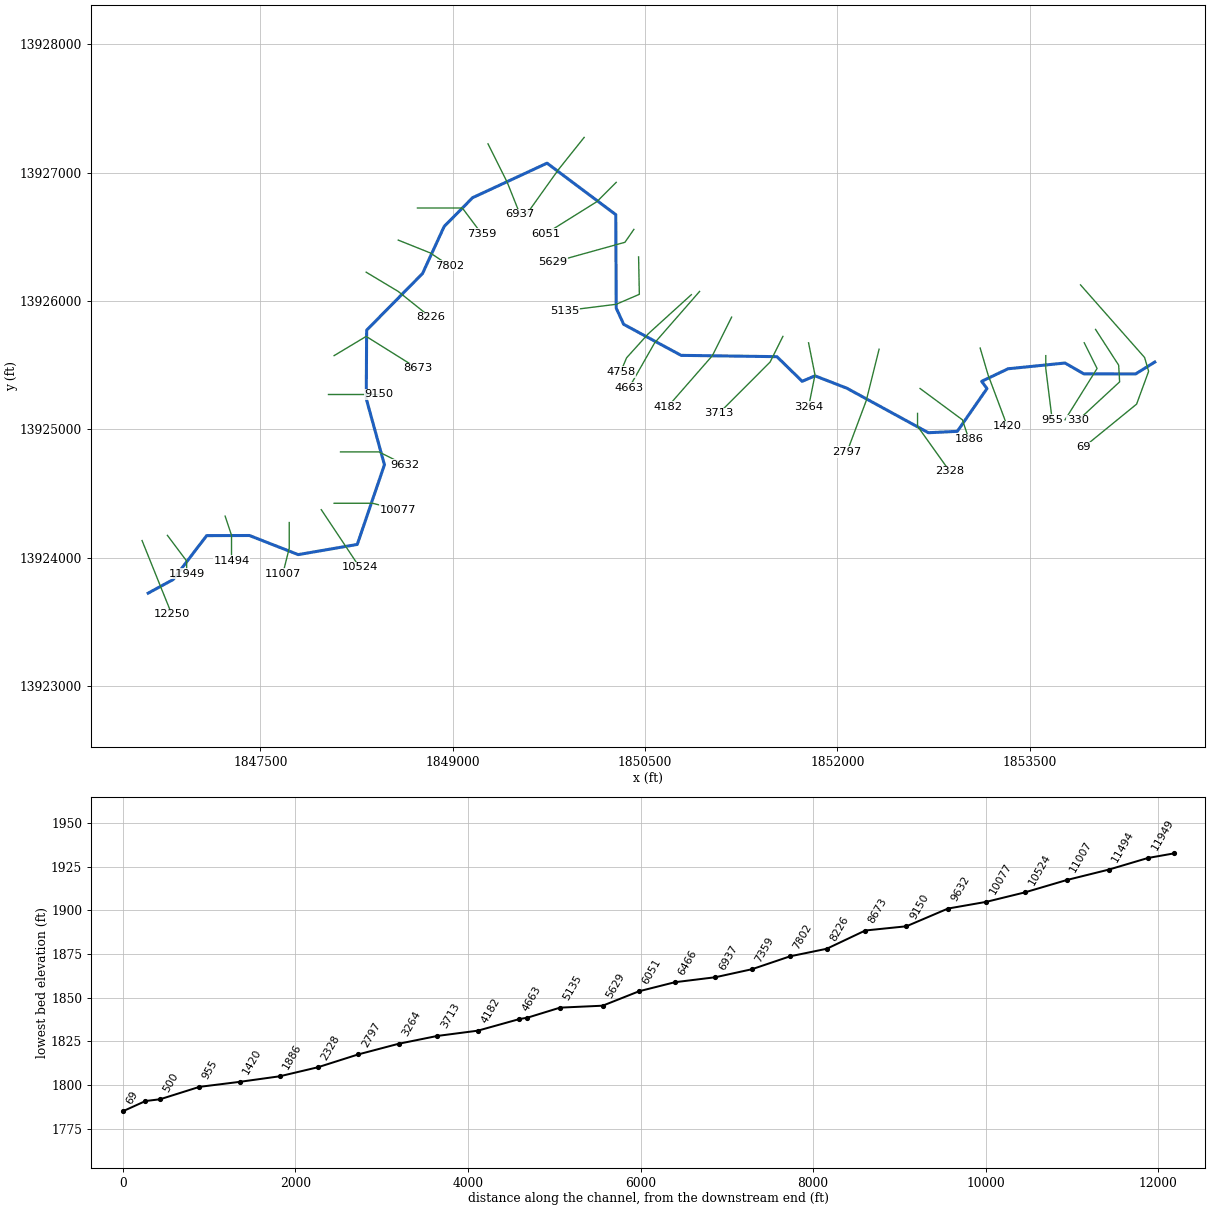
--- Stream0305.prj (project) ---

Proj Title=Stream0305 Base Level Engineering
Current Plan=p01
Default Exp/Contr=0.3,0.1
English Units
Geom File=g01
Flow File=f01
Plan File=p01
Y Axis Title=Elevation
X Axis Title(PF)=Main Channel Distance
X Axis Title(XS)=Station
BEGIN DESCRIPTION:
Stream0305
END DESCRIPTION:
DSS Export Rating Curves= 0
DSS Export Rating Curve Sorted= 0
DSS Export Volume Flow Curves= 0
DXF OffsetX= 0
DXF OffsetY= 0
DXF ScaleX= 1
DXF ScaleY= 10

--- Stream0305.p01 (plan) ---

Plan Title=Multiple Run
Short Identifier=Multiple
Geom File=g01
Flow File=f01
Subcritical Flow
K Sum by GR= 0
Std Step Tol= 0.01
Critical Tol= 0.01
Num of Std Step Trials= 20
Max Error Tol= 0.3
Flow Tol Ratio= 0.001
Split Flow NTrial= 30
Split Flow Tol= 0.02
Split Flow Ratio= 0.02
Log Output Level= 0
Friction Slope Method= 1
Unsteady Friction Slope Method= 2
Unsteady Bridges Friction Slope Method= 1
Parabolic Critical Depth
Global Vel Dist=  1 , 1 , 1
Global Log Level= 0
CheckData=True
Encroach Param= -1, 0, 0, 0
BEGIN DESCRIPTION:
Multiple Run
END DESCRIPTION:

--- Stream0305.f01 (steady flow) ---

Flow Title=Multiple
Number of Profiles=7
Profile Names=10-year,25-year,50-year,1pct_min,100-year,1pct_plu,500-year
River Rch & RM= Stream0305,Reach-1,12250
    2219    3965    5700    3951    7884   15731   14923
River Rch & RM= Stream0305,Reach-1,6466
    2283    4082    5869    4068    8117   16195   15364
River Rch & RM= Stream0305,Reach-1,4758
    2469    4428    6380    4431    8840   17639   16797
River Rch & RM= Stream0305,Reach-1,3264
    2684    4832    6979    4857    9691   19336   18490
River Rch & RM= Stream0305,Reach-1,1420
    2932    5300    7675    5354   10683   21316   20485
Boundary for River Rch & Prof#=Stream0305,Reach-1,1
Up Type=0
Dn Type=3
Dn Slope=0.005
Boundary for River Rch & Prof#=Stream0305,Reach-1,2
Up Type=0
Dn Type=3
Dn Slope=0.005
Boundary for River Rch & Prof#=Stream0305,Reach-1,3
Up Type=0
Dn Type=3
Dn Slope=0.005
Boundary for River Rch & Prof#=Stream0305,Reach-1,4
Up Type=0
Dn Type=3
Dn Slope=0.005
Boundary for River Rch & Prof#=Stream0305,Reach-1,5
Up Type=0
Dn Type=3
Dn Slope=0.005
Boundary for River Rch & Prof#=Stream0305,Reach-1,6
Up Type=0
Dn Type=3
Dn Slope=0.005
Boundary for River Rch & Prof#=Stream0305,Reach-1,7
Up Type=0
Dn Type=3
Dn Slope=0.005

--- Stream0305.g01 (geometry) ---

Geom Title=Existing Conditions
Program Version=4.10

River Reach=Stream0305      ,Reach-1
Reach XY= 30
        1846625.       13923725.      1846819.38     13923830.62
      1847080.84     13924172.95      1847414.56     13924173.94
      1847795.03     13924025.07      1848255.57     13924104.36
      1848467.44       13924725.      1848325.51     13925240.21
      1848328.76     13925773.44      1848764.61      13926214.9
      1848933.14     13926581.06      1849154.91     13926805.22
       1849735.7      13927074.3      1850271.39     13926673.52
      1850275.06     13925945.03      1850333.12     13925818.93
      1850780.93     13925577.24      1851528.34     13925567.01
        1851725.       13925375.      1851824.97     13925417.72
       1852073.5     13925321.38      1852709.51     13924974.51
      1852935.12     13924985.34      1853166.23     13925318.33
        1853125.       13925375.      1853330.94     13925472.74
      1853775.01     13925517.47      1853921.68     13925433.04
       1854325.1     13925432.31        1854475.       13925525.

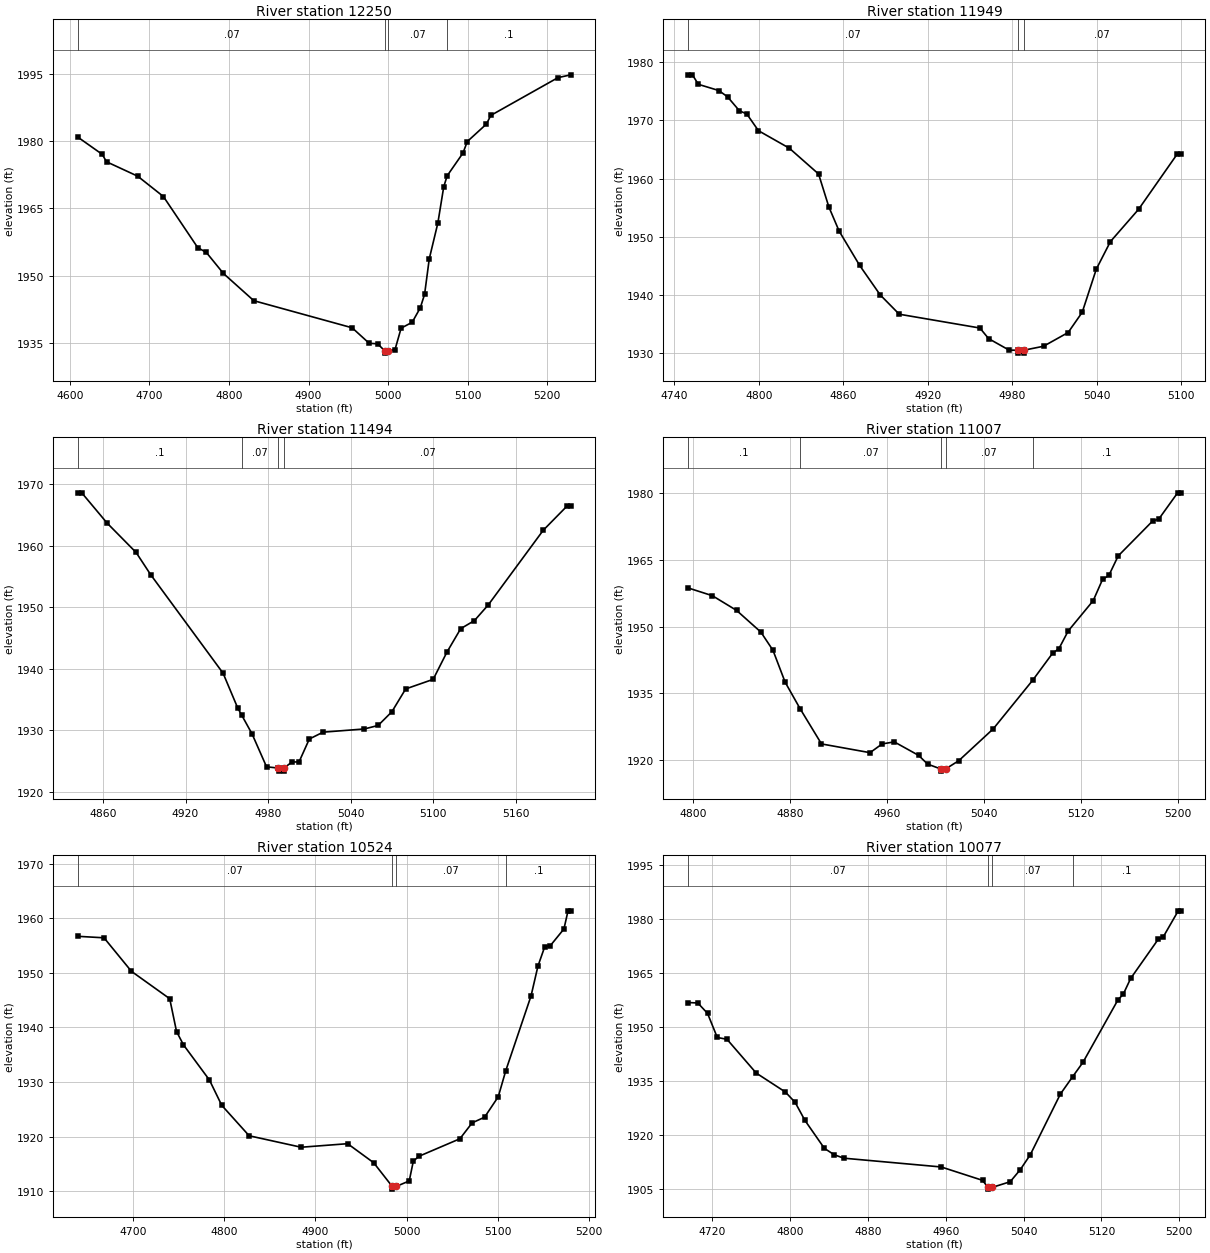
Type RM Length L Ch R = 1 ,12250   ,301,301,301
BEGIN DESCRIPTION:
Stream0305 27.0
END DESCRIPTION:
XS GIS Cut Line= 2
      1846577.16     13924134.54      1846808.99     13923560.05
#Sta/Elev= 30
  4610.2 1980.89  4640.6 1977.08    4646 1975.42  4685.2  1972.2  4717.5 1967.66
  4760.7 1956.24  4771.5 1955.17    4793 1950.47  4831.2 1944.39  4954.8 1938.34
  4976.3 1934.87  4986.8 1934.77  4995.9 1933.18  4996.2 1932.68    5000 1933.18
  5008.7 1933.45  5016.4 1938.26  5030.3 1939.57  5040.5  1942.8  5045.9 1945.81
  5051.8 1953.75  5062.6 1961.74    5070 1969.85  5074.3 1972.29  5094.2 1977.38
  5099.6 1979.94  5123.7 1983.85  5129.1 1985.77  5213.6 1994.21  5229.7 1994.84
#Mann= 4 ,-1 , 0
  4610.2     .07       0  4995.9     .05       0    5000     .07       0
  5074.3      .1       0
Bank Sta=4995.9,5000
XS Rating Curve= 0 ,0
Exp/Cntr=0.3,0.1

Type RM Length L Ch R = 1 ,11949   ,455,455,455
BEGIN DESCRIPTION:
Stream0305 26.0
END DESCRIPTION:
XS GIS Cut Line= 3
        1846775.       13924175.        1846925.       13923975.
        1846925.       13923875.
#Sta/Elev= 30
  4749.7 1977.83  4752.8 1977.83    4757  1976.2  4771.6 1975.13  4777.8 1974.04
  4786.2 1971.65  4791.4 1971.12  4799.7 1968.24  4821.6 1965.24  4842.4 1960.81
  4849.7 1955.16    4857 1951.01  4871.6 1945.11  4886.2 1940.05  4899.7 1936.74
    4957 1934.37  4963.2 1932.55  4977.8 1930.57  4984.1 1930.56  4984.4 1930.06
    4988 1930.06  4988.2 1930.56  5002.2 1931.24  5019.7  1933.6  5029.7 1937.08
  5039.7 1944.48  5049.7  1949.2  5069.7 1954.74  5097.2 1964.24  5099.7 1964.24
#Mann= 3 ,-1 , 0
  4749.7     .07       0  4984.1     .05       0  4988.2     .07       0
Bank Sta=4984.1,4988.2
XS Rating Curve= 0 ,0
Exp/Cntr=0.3,0.1

Type RM Length L Ch R = 1 ,11494   ,487,487,487
BEGIN DESCRIPTION:
Stream0305 25.0
END DESCRIPTION:
XS GIS Cut Line= 3
      1847224.99     13924325.02        1847275.       13924175.
        1847275.     13923975.03
#Sta/Elev= 30
  4841.9  1968.6  4844.6  1968.6    4863 1963.69  4884.1 1958.91  4894.6 1955.33
  4947.3  1939.3  4957.9 1933.67  4960.7 1932.54  4968.4 1929.42  4978.9 1924.09
  4987.4 1923.89  4987.7 1923.39  4991.3 1923.39  4991.6 1923.89  4997.4 1924.88
  5002.5 1924.88    5010 1928.61    5020 1929.72    5050 1930.24    5060 1930.81
    5070 1933.04    5080 1936.74    5100  1938.3    5110 1942.72    5120 1946.53
    5130 1947.85    5140 1950.38    5180 1962.52  5197.5  1966.5    5200  1966.5
#Mann= 4 ,-1 , 0
  4841.9      .1       0  4960.7     .07       0  4987.4     .05       0
  4991.6     .07       0
Bank Sta=4987.4,4991.6
XS Rating Curve= 0 ,0
Exp/Cntr=0.3,0.1

Type RM Length L Ch R = 1 ,11007   ,483,483,483
BEGIN DESCRIPTION:
Stream0305 24.0
END DESCRIPTION:
XS GIS Cut Line= 3
        1847725.     13924275.02        1847725.       13924075.
      1847674.99     13923874.97
#Sta/Elev= 30
  4795.8 1958.71  4815.8 1956.96  4835.8 1953.64  4855.8 1948.76  4865.8 1944.65
  4875.8 1937.48  4888.2 1931.47  4905.8 1923.55  4945.8 1921.58  4955.8 1923.55
  4965.8 1924.01  4985.8 1920.98  4993.3    1919    5004 1917.92  5004.3 1917.42
  5008.2 1917.92    5019 1919.78  5047.4 1926.95  5080.1 1937.97  5096.3 1943.98
  5101.5 1945.01  5109.2 1949.01  5129.8 1955.84  5137.5 1960.62  5142.7 1961.52
  5150.4 1965.92  5178.8 1973.79  5183.9 1974.24  5199.4 1980.14    5202 1980.14
#Mann= 5 ,-1 , 0
  4795.8      .1       0  4888.2     .07       0    5004     .05       0
  5008.2     .07       0  5080.1      .1       0
Bank Sta=5004,5008.2
XS Rating Curve= 0 ,0
Exp/Cntr=0.3,0.1

Type RM Length L Ch R = 1 ,10524   ,447,447,447
BEGIN DESCRIPTION:
Stream0305 23.0
END DESCRIPTION:
XS GIS Cut Line= 3
      1847975.01     13924374.98        1848175.       13924075.
      1848274.99     13923925.01
#Sta/Elev= 30
  4639.4 1956.67  4667.9  1956.4    4698 1950.26    4740 1945.25  4747.5 1939.24
  4755.1  1936.8  4783.6 1930.36  4797.1 1925.73  4827.2 1920.15  4884.3 1918.05
  4935.3  1918.7  4963.9 1915.21  4984.2 1910.88  4984.5 1910.38  4988.7 1910.88
  5002.9 1911.88  5007.4  1915.5  5013.5 1916.39  5058.5  1919.6    5072 1922.52
  5085.6 1923.55  5100.6 1927.29  5108.9 1932.09  5136.6 1945.76  5144.2 1951.23
  5151.7  1954.8  5157.7 1954.95  5172.7 1958.02  5177.2 1961.34  5180.2 1961.34
#Mann= 4 ,-1 , 0
  4639.4     .07       0  4984.2     .05       0  4988.7     .07       0
  5108.9      .1       0
Bank Sta=4984.2,4988.7
XS Rating Curve= 0 ,0
Exp/Cntr=0.3,0.1

Type RM Length L Ch R = 1 ,10077   ,445,445,445
BEGIN DESCRIPTION:
Stream0305 22.0
END DESCRIPTION:
XS GIS Cut Line= 3
      1848075.03       13924425.        1848375.       13924425.
      1848574.98     13924375.01
#Sta/Elev= 30
  4695.4 1956.82  4705.4  1956.7  4715.4 1953.81  4725.4 1947.11  4735.4  1946.6
  4765.4 1937.22  4795.4 1931.94  4805.4 1929.06  4815.4 1924.08  4835.4  1916.3
  4845.4 1914.53  4855.4 1913.56  4955.4 1911.12  4997.9  1907.4  5003.4 1905.46
  5003.7 1904.96    5008 1905.46  5026.3 1907.02  5036.6 1910.36  5046.9  1914.5
  5077.8 1931.37  5090.5 1936.24    5101 1940.19  5137.1 1957.63  5142.3 1959.07
    5150 1963.51  5178.3 1974.39  5183.5 1975.07  5198.9 1982.31  5201.5 1982.31
#Mann= 4 ,-1 , 0
  4695.4     .07       0  5003.4     .05       0    5008     .07       0
  5090.5      .1       0
Bank Sta=5003.4,5008
XS Rating Curve= 0 ,0
Exp/Cntr=0.3,0.1

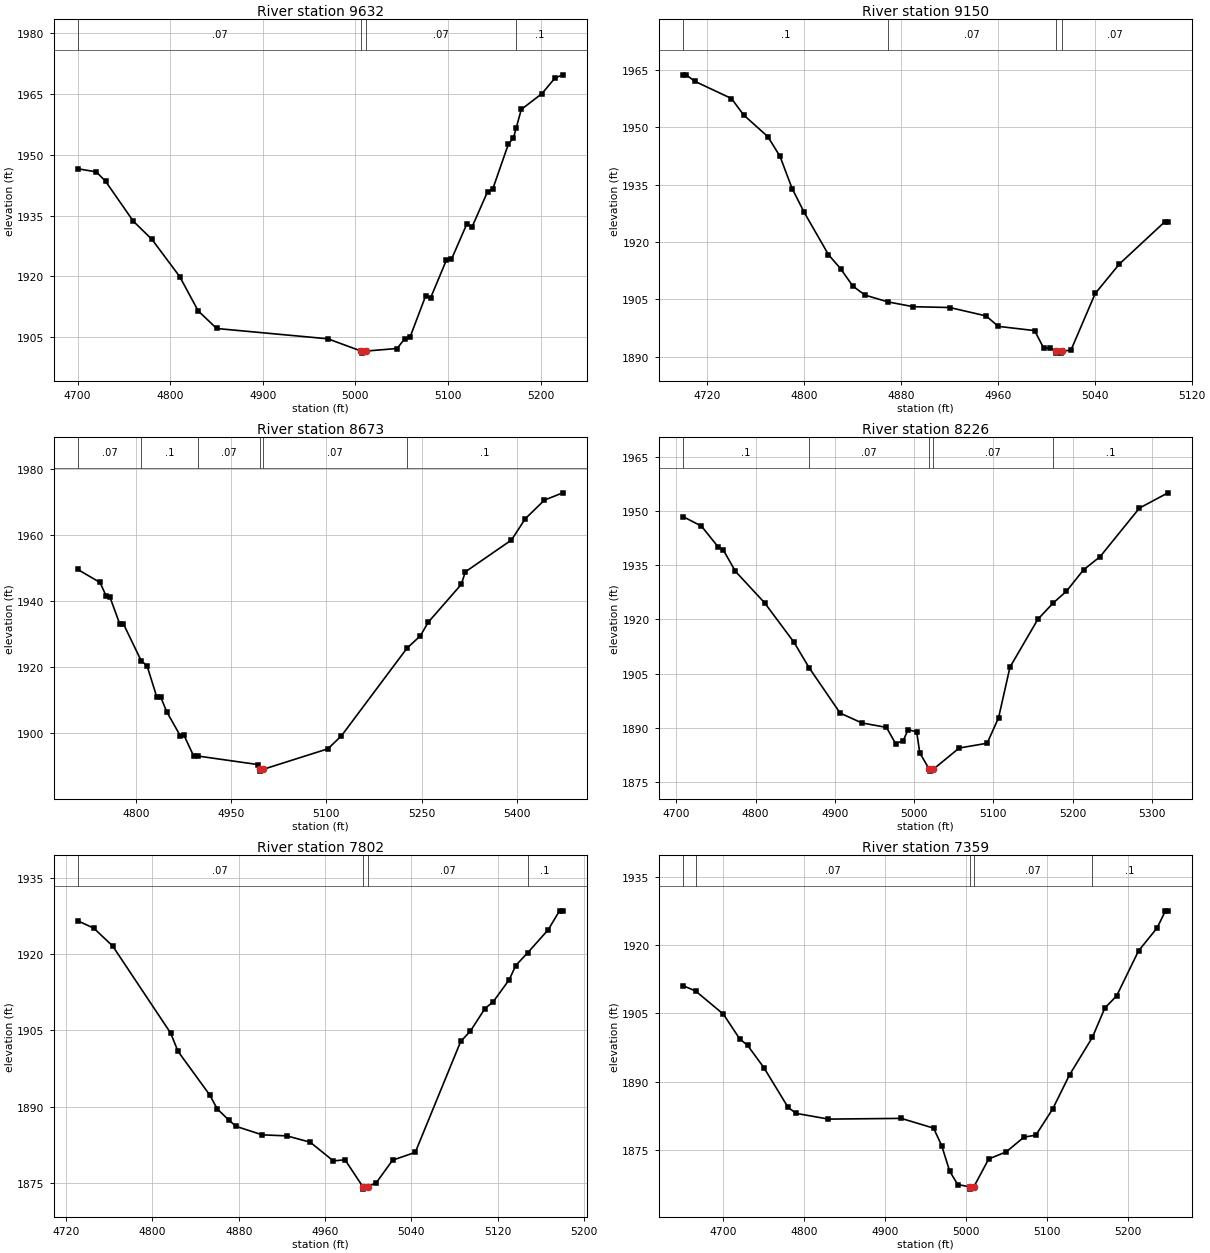
Type RM Length L Ch R = 1 ,9632    ,482,482,482
BEGIN DESCRIPTION:
Stream0305 21.0
END DESCRIPTION:
XS GIS Cut Line= 3
      1848124.95       13924825.        1848425.       13924825.
      1848625.04     13924724.98
#Sta/Elev= 30
  4700.3 1946.55  4720.3 1945.78  4730.3 1943.46  4760.3 1933.61  4780.3 1929.16
  4810.3 1919.99  4830.3 1911.53  4850.3 1907.18  4970.3 1904.64  5006.4 1901.61
  5006.7 1901.11    5011 1901.61  5045.1 1902.25  5053.5  1904.7    5059    1905
  5075.8 1915.12  5081.4 1914.78  5098.2 1923.96  5103.8 1924.22  5120.5 1932.99
  5126.1 1932.22  5142.9 1940.94  5148.5 1941.62  5165.3 1952.63  5170.8 1954.17
  5173.7 1956.59  5179.2 1961.17  5201.6 1965.08  5215.6 1968.91    5224  1969.7
#Mann= 4 ,-1 , 0
  4700.3     .07       0  5006.4     .05       0    5011     .07       0
  5173.7      .1       0
Bank Sta=5006.4,5011
XS Rating Curve= 0 ,0
Exp/Cntr=0.3,0.1

Type RM Length L Ch R = 1 ,9150    ,477,477,477
BEGIN DESCRIPTION:
Stream0305 20.0
END DESCRIPTION:
XS GIS Cut Line= 3
      1848025.01       13925275.        1848325.       13925275.
      1848425.01       13925275.
#Sta/Elev= 30
  4700.4 1963.75  4702.9 1963.75  4710.4 1962.01  4740.4 1957.55  4750.4 1953.26
  4770.4 1947.57  4780.4 1942.43  4790.4 1934.01  4800.4 1927.75  4820.4 1916.71
  4830.4 1913.03  4840.4 1908.53  4850.4 1906.15  4869.4 1904.36  4890.4  1903.1
  4920.4 1902.89  4950.4 1900.69  4960.4 1897.96  4990.4 1896.85  4997.9 1892.27
  5002.9 1892.27    5008 1891.46  5008.4 1890.96  5012.4 1890.96  5012.7 1891.46
  5020.4 1891.75  5040.4 1906.56  5060.4 1914.29  5097.9 1925.35  5100.4 1925.35
#Mann= 4 ,-1 , 0
  4700.4      .1       0  4869.4     .07       0    5008     .05       0
  5012.7     .07       0
Bank Sta=5008,5012.7
XS Rating Curve= 0 ,0
Exp/Cntr=0.3,0.1

Type RM Length L Ch R = 1 ,8673    ,447,447,447
BEGIN DESCRIPTION:
Stream0305 19.0
END DESCRIPTION:
XS GIS Cut Line= 3
      1848074.98     13925574.99        1848325.       13925725.
      1848725.03     13925474.98
#Sta/Elev= 30
  4708.8 1949.63  4743.8  1945.7  4753.5 1941.57  4759.4 1941.27  4774.9  1933.1
  4780.7 1933.12  4808.8  1921.9  4817.7 1920.53  4833.2 1910.96    4839 1911.13
  4848.8 1906.52  4870.1 1899.26    4876 1899.39  4891.5 1892.98  4898.6 1893.09
  4992.6 1890.52  4995.1 1889.04  4995.5 1888.54  4999.8 1889.04  5102.4  1895.3
  5123.6 1899.19  5226.9 1925.78    5248 1929.53  5260.4 1933.65  5312.3  1945.1
  5318.8 1948.92  5391.3 1958.55  5413.1    1965  5443.2 1970.65  5472.1 1972.86
#Mann= 6 ,-1 , 0
  4708.8     .07       0  4808.8      .1       0  4898.6     .07       0
  4995.1     .05       0  4999.8     .07       0  5226.9      .1       0
Bank Sta=4995.1,4999.8
XS Rating Curve= 0 ,0
Exp/Cntr=0.3,0.1

Type RM Length L Ch R = 1 ,8226    ,424,424,424
BEGIN DESCRIPTION:
Stream0305 18.0
END DESCRIPTION:
XS GIS Cut Line= 3
      1848325.01       13926225.        1848575.       13926075.
        1848825.       13925875.
#Sta/Elev= 30
  4708.5 1948.45  4731.8 1945.81  4753.2 1939.96    4759 1939.34  4774.6 1933.32
  4811.5 1924.59  4848.4 1913.73  4867.5 1906.68  4906.7 1894.13    4934 1891.41
  4965.1 1890.17  4976.7 1885.67  4986.4 1886.52  4992.3 1889.55  5003.2 1888.94
  5007.2  1883.1  5019.2 1878.58  5019.5 1878.08  5024.1 1878.58  5056.9 1884.47
  5092.1 1885.79  5106.5 1892.81  5120.9 1906.82  5156.1 1920.06  5175.4 1924.56
  5192.1 1927.81  5213.7 1933.73  5234.6 1937.37  5284.2  1950.8  5320.2 1955.02
#Mann= 5 ,-1 , 0
  4708.5      .1       0  4867.5     .07       0  5019.2     .05       0
  5024.1     .07       0  5175.4      .1       0
Bank Sta=5019.2,5024.1
XS Rating Curve= 0 ,0
Exp/Cntr=0.3,0.1

Type RM Length L Ch R = 1 ,7802    ,443,443,443
BEGIN DESCRIPTION:
Stream0305 17.0
END DESCRIPTION:
XS GIS Cut Line= 3
      1848575.03     13926474.99        1848825.       13926375.
        1848975.       13926275.
#Sta/Elev= 30
  4730.8 1926.59  4745.6 1925.15  4763.1 1921.64  4816.9 1904.48  4823.7 1900.89
  4853.3 1892.25    4860 1889.57  4870.8 1887.36  4877.5 1886.13  4901.7 1884.46
  4924.6 1884.25  4946.2 1883.01  4967.7 1879.32  4978.5 1879.55  4994.9 1874.27
  4995.2 1873.77  4999.8 1874.27  5007.5 1875.04  5022.6 1879.47  5043.6 1881.01
  5085.7 1902.84  5094.7 1904.88  5108.2 1909.33  5115.7 1910.62  5130.7    1915
  5136.7 1917.79  5147.7 1920.28  5166.8 1924.83  5177.3 1928.56  5180.3 1928.56
#Mann= 4 ,-1 , 0
  4730.8     .07       0  4994.9     .05       0  4999.8     .07       0
  5147.7      .1       0
Bank Sta=4994.9,4999.8
XS Rating Curve= 0 ,0
Exp/Cntr=0.3,0.1

Type RM Length L Ch R = 1 ,7359    ,422,422,422
BEGIN DESCRIPTION:
Stream0305 16.0
END DESCRIPTION:
XS GIS Cut Line= 3
      1848724.96       13926725.        1849075.       13926725.
      1849224.97     13926525.03
#Sta/Elev= 30
    4650  1911.1  4665.6 1909.91    4700 1904.82    4720 1899.43    4730 1897.94
    4750 1893.09    4780 1884.34    4790 1883.02    4830 1881.76    4920 1881.92
    4960 1879.78    4970 1875.95    4980 1870.28    4990 1867.37  5004.9 1866.87
  5005.2 1866.37  5009.8 1866.87  5028.2 1872.99    5050 1874.57  5071.9 1877.81
  5086.5 1878.22  5107.3 1883.96  5128.2 1891.48  5156.4  1899.7  5171.9 1906.18
  5186.5 1908.85  5213.6 1918.74  5236.5 1923.77  5246.9 1927.54    5250 1927.54
#Mann= 5 ,-1 , 0
    4650      .1       0  4665.6     .07       0  5004.9     .05       0
  5009.8     .07       0  5156.4      .1       0
Bank Sta=5004.9,5009.8
XS Rating Curve= 0 ,0
Exp/Cntr=0.3,0.1

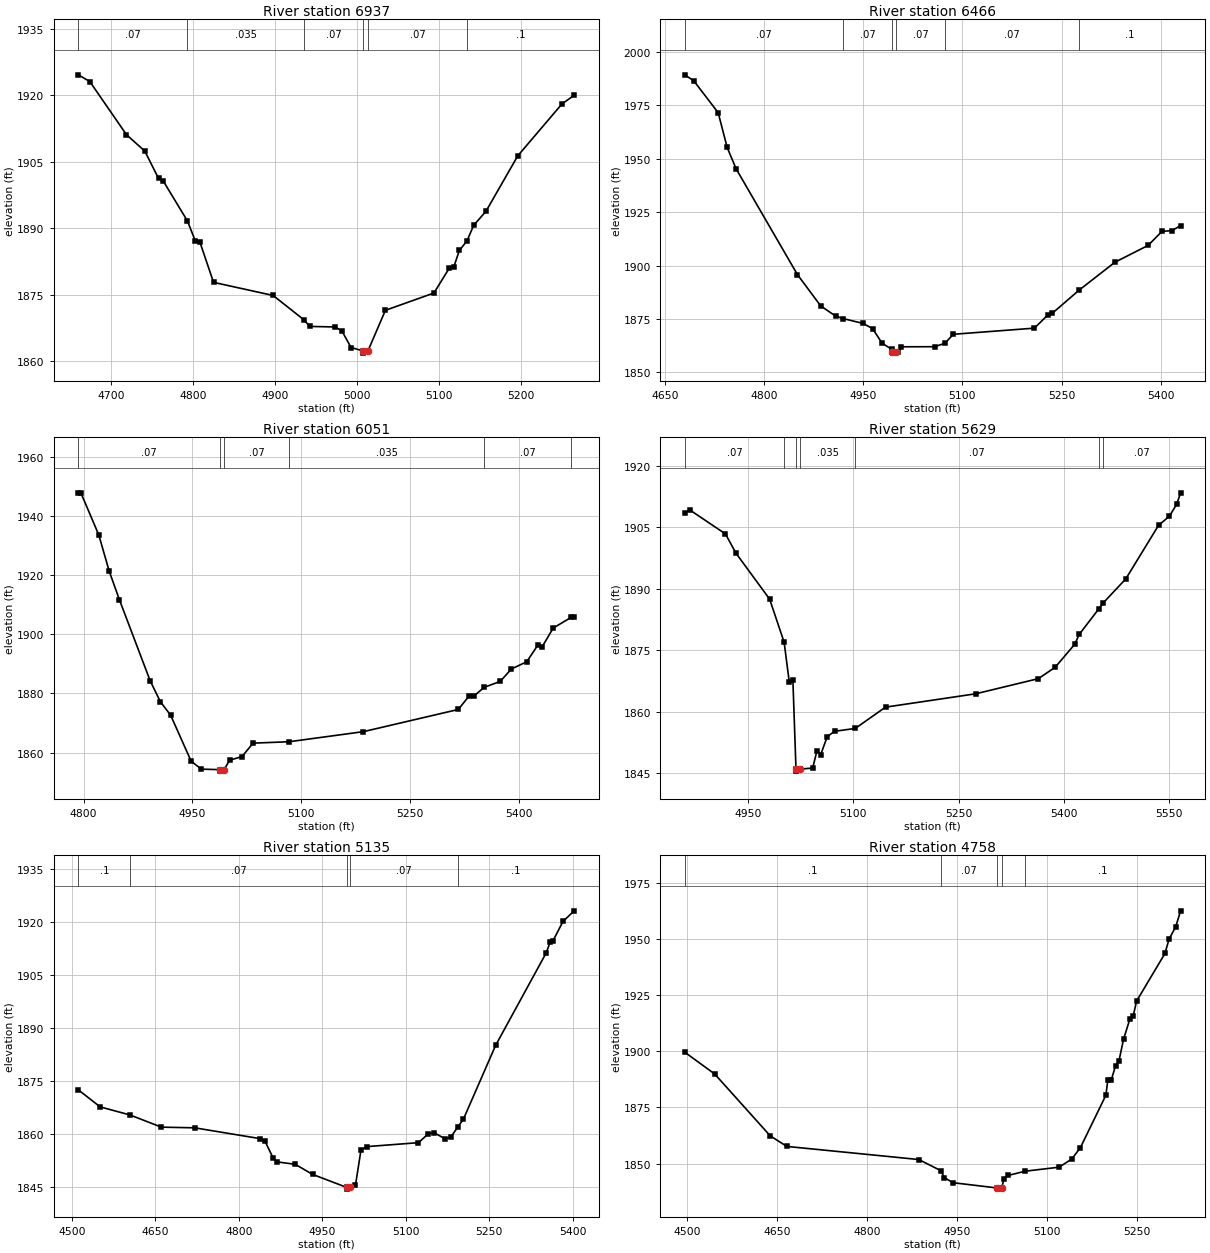
Type RM Length L Ch R = 1 ,6937    ,471,471,471
BEGIN DESCRIPTION:
Stream0305 15.0
END DESCRIPTION:
XS GIS Cut Line= 3
      1849274.99     13927225.01        1849425.       13926925.
      1849525.01     13926674.98
#Sta/Elev= 30
  4660.4 1924.66  4674.4 1923.14  4719.1 1911.14  4741.5 1907.43  4758.2 1901.26
  4763.8 1900.73  4793.4 1891.67    4803 1887.17  4808.6 1886.91  4825.3 1877.79
    4898 1874.82  4935.2 1869.37  4942.7 1867.83  4973.5 1867.71  4981.8 1866.82
    4993 1863.07  5007.6  1862.3  5008.1  1861.8  5013.6  1862.3  5034.9 1871.47
  5094.1 1875.38  5112.9 1881.03  5118.3 1881.27  5125.1 1884.99  5134.4 1887.15
  5142.6 1890.69  5157.4 1893.79  5196.4 1906.38  5250.3  1918.1  5265.1 1920.03
#Mann= 6 ,-1 , 0
  4660.4     .07       0  4793.4    .035       0  4935.2     .07       0
  5007.6     .05       0  5013.6     .07       0  5134.4      .1       0
Bank Sta=5007.6,5013.6
XS Rating Curve= 0 ,0
Exp/Cntr=0.3,0.1

Type RM Length L Ch R = 1 ,6466    ,415,415,415
BEGIN DESCRIPTION:
Stream0305 14.0
END DESCRIPTION:
XS GIS Cut Line= 3
      1850025.03     13927275.03        1849825.       13927025.
      1849575.01     13926675.01
#Sta/Elev= 30
  4679.9 1989.37  4693.5 1986.57  4730.4 1971.63    4744 1955.34  4757.6 1945.29
  4850.4 1895.71  4885.6 1881.05  4908.1  1876.3  4919.9 1875.09  4949.7 1872.85
  4964.1 1870.41  4978.5 1863.56  4992.9 1860.78  4993.8 1859.43  4994.3 1858.93
  4999.9 1859.43  5003.2 1859.43  5007.5  1861.9  5057.9 1861.94  5073.7 1863.57
  5086.1 1867.76    5209 1870.64  5229.9 1877.02    5236 1877.61  5276.2 1888.35
  5330.7 1901.52  5381.1 1909.44    5402 1915.99  5416.7 1916.34  5430.2 1918.65
#Mann= 6 ,-1 , 0
  4679.9     .07       0  4919.9     .07       0  4993.8     .05       0
  4999.9     .07       0  5073.7     .07       0  5276.2      .1       0
Bank Sta=4993.8,4999.9
XS Rating Curve= 0 ,0
Exp/Cntr=0.3,0.1

Type RM Length L Ch R = 1 ,6051    ,422,422,422
BEGIN DESCRIPTION:
Stream0305 13.0
END DESCRIPTION:
XS GIS Cut Line= 3
      1850274.99     13926924.99        1850125.       13926775.
      1849725.02     13926525.01
#Sta/Elev= 30
  4792.7 1947.82  4796.2 1947.82    4821 1933.53  4835.1 1921.47  4849.3 1911.72
  4891.7 1884.33  4905.8 1877.24    4920 1872.66  4948.3  1857.1  4962.4 1854.43
  4987.6 1854.26  4988.1 1853.76  4993.7 1854.26  5001.3 1857.44  5018.4 1858.68
  5033.7 1863.22  5083.3 1863.69  5185.8  1867.1  5316.7  1874.6  5332.1 1879.31
    5338 1879.08  5352.3 1882.07  5374.5 1884.07  5389.8 1888.25  5411.1 1890.73
  5426.4 1896.34  5432.3 1895.76  5447.6  1902.1  5472.3 1905.73  5476.5 1905.81
#Mann= 6 ,-1 , 0
  4792.7     .07       0  4987.6     .05       0  4993.7     .07       0
  5083.3    .035       0  5352.3     .07       0  5472.3      .1       0
Bank Sta=4987.6,4993.7
XS Rating Curve= 0 ,0
Exp/Cntr=0.3,0.1

Type RM Length L Ch R = 1 ,5629    ,494,494,494
BEGIN DESCRIPTION:
Stream0305 12.0
END DESCRIPTION:
XS GIS Cut Line= 3
      1850412.55     13926558.38      1850342.84     13926457.89
      1849779.61     13926301.65
#Sta/Elev= 30
  4859.7 1908.51    4867 1909.16  4917.7 1903.32  4932.6 1898.64  4980.7 1887.41
  5001.3 1876.91  5008.6 1867.26  5013.8 1867.61  5018.2 1845.99  5018.7 1845.49
  5024.3 1845.99    5042 1846.24  5048.1 1850.45  5053.3 1849.45  5062.8 1853.91
  5073.2  1855.2  5102.7  1855.9  5145.8 1861.09  5274.5 1864.35  5363.7 1868.04
  5387.7 1870.82  5415.6 1876.43  5421.9 1878.82  5449.9 1885.06  5456.4 1886.55
  5488.3 1892.36  5535.1 1905.44  5550.5 1907.65  5560.9 1910.57  5566.5 1913.35
#Mann= 7 ,-1 , 0
  4859.7     .07       0  5001.3    .035       0  5018.2     .05       0
  5024.3    .035       0  5102.7     .07       0  5449.9      .1       0
  5456.4     .07       0
Bank Sta=5018.2,5024.3
XS Rating Curve= 0 ,0
Exp/Cntr=0.3,0.1

Type RM Length L Ch R = 1 ,5135    ,377,377,377
BEGIN DESCRIPTION:
Stream0305 11.0
END DESCRIPTION:
XS GIS Cut Line= 4
      1850449.45     13926344.16      1850455.35     13926052.87
        1850275.       13925975.      1849875.01       13925925.
#Sta/Elev= 30
  4511.8 1872.48    4551 1867.66  4605.1 1865.35    4661 1861.92    4721 1861.73
  4838.6 1858.67  4847.1 1857.97  4862.1 1853.11  4868.9 1852.09  4901.6  1851.4
  4932.7 1848.55  4993.8 1844.88  4994.3 1844.38    5000 1844.88  5009.7 1845.41
  5019.7 1855.48  5029.8 1856.41    5123 1857.53  5140.7 1860.05  5150.8 1860.39
  5170.9 1858.59    5181  1859.1  5193.5 1861.93  5203.7 1864.18  5261.6 1885.07
  5352.3  1911.2  5359.9 1914.42  5364.9 1914.74  5382.6 1920.13  5402.7 1923.15
#Mann= 5 ,-1 , 0
  4511.8      .1       0  4605.1     .07       0  4993.8     .05       0
    5000     .07       0  5193.5      .1       0
Bank Sta=4993.8,5000
XS Rating Curve= 0 ,0
Exp/Cntr=0.3,0.1

Type RM Length L Ch R = 1 ,4758    ,95,95,95
BEGIN DESCRIPTION:
Stream0305 10.1
END DESCRIPTION:
XS GIS Cut Line= 4
      1850860.76     13926049.88      1850524.84     13925745.21
      1850355.57     13925557.71      1850309.35      13925447.3
#Sta/Elev= 30
  4496.3  1899.6  4546.1  1889.9  4638.7 1862.33  4666.3 1857.65    4886 1851.82
  4922.6 1846.88  4928.6 1843.77  4942.8 1841.51    5017 1839.14  5017.5 1838.64
  5023.9 1839.14  5027.9 1843.21  5034.7 1844.73  5063.1 1846.62  5119.8 1848.41
  5140.8 1852.06    5155 1857.02  5197.6 1880.44  5200.9 1887.29  5206.6 1887.29
  5213.8 1893.57  5219.2 1895.49    5227 1905.31  5237.6 1914.43    5243 1915.57
  5248.7 1922.34    5296 1943.56  5302.9 1950.01  5313.8 1955.37  5322.1 1962.55
#Mann= 5 ,-1 , 0
  4496.3      .1       0  4922.6     .07       0    5017     .05       0
  5023.9     .07       0  5063.1      .1       0
Bank Sta=5017,5023.9
XS Rating Curve= 0 ,0
Exp/Cntr=0.3,0.1

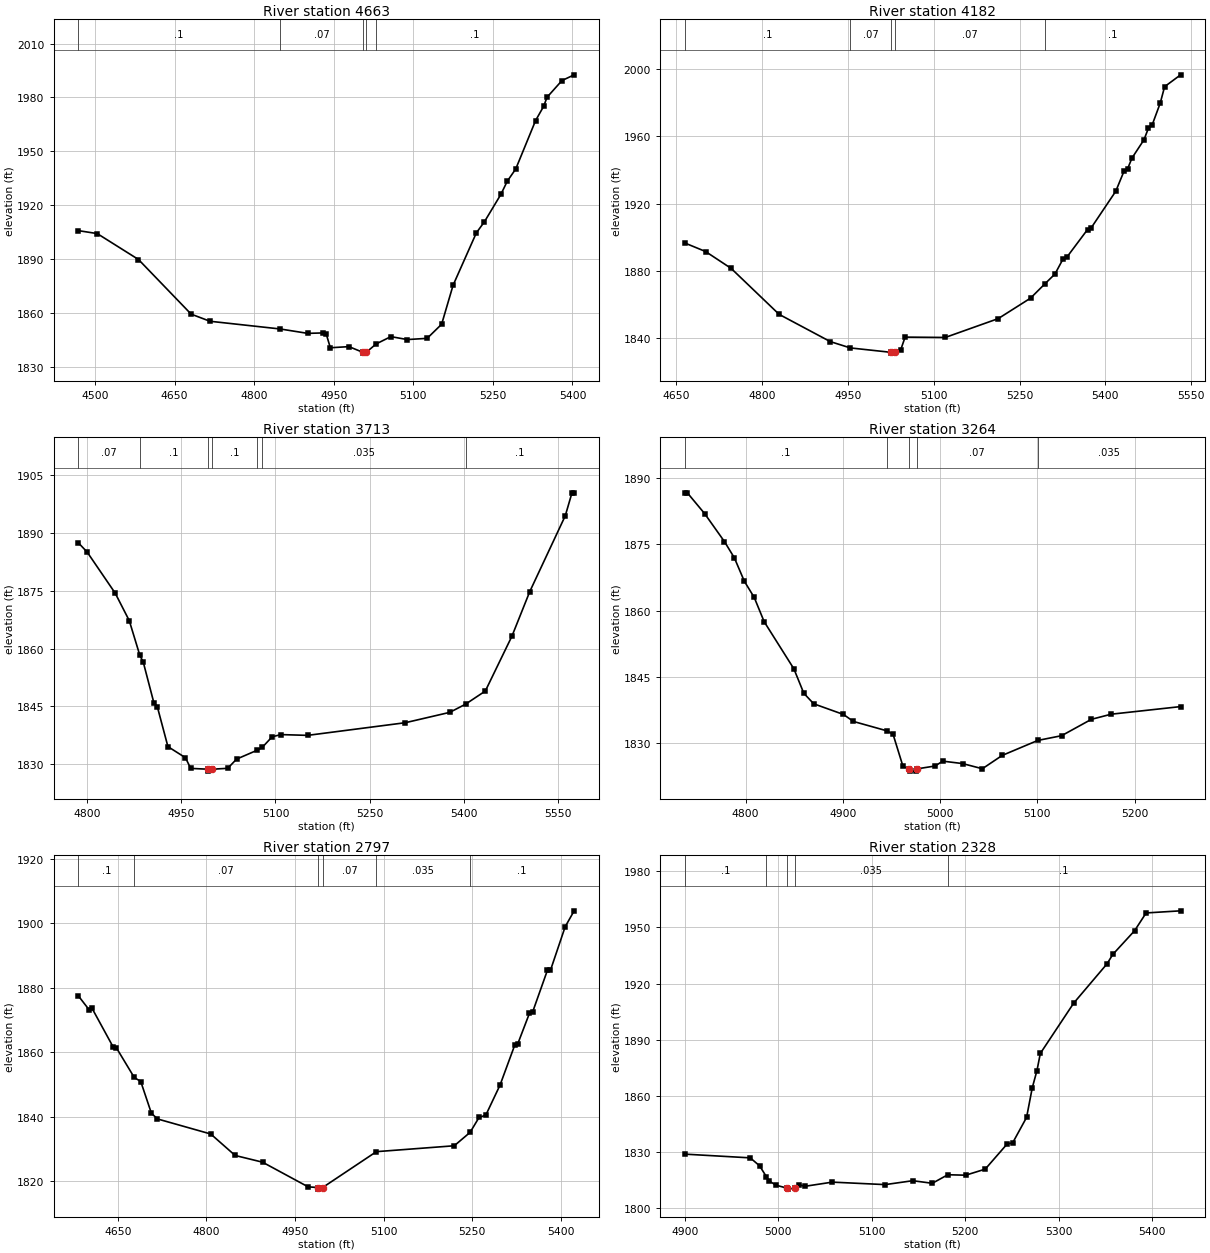
Type RM Length L Ch R = 1 ,4663    ,481,481,481
BEGIN DESCRIPTION:
Stream0305 10.0
END DESCRIPTION:
XS GIS Cut Line= 3
      1850924.98     13926074.98        1850575.       13925675.
        1850375.       13925325.
#Sta/Elev= 30
  4468.6 1905.94  4504.2  1904.3    4582 1889.88  4681.2 1859.51  4716.8 1855.54
  4848.9 1851.26  4900.9 1848.81  4929.4 1849.05    4936 1848.33  4943.6 1840.81
  4978.7 1841.43  5004.6 1838.32  5005.1 1837.82  5011.5 1838.32    5030 1842.94
  5057.7    1847  5088.6 1845.36  5126.1 1846.04  5153.4 1853.88    5175 1875.58
  5218.9 1904.73    5234 1910.84    5265 1926.05  5277.2 1933.47  5293.1 1940.23
  5330.5 1967.15  5345.6 1975.02  5352.1 1980.11  5380.2 1989.39  5403.2 1992.58
#Mann= 5 ,-1 , 0
  4468.6      .1       0  4848.9     .07       0  5004.6     .05       0
  5011.5     .07       0    5030      .1       0
Bank Sta=5004.6,5011.5
XS Rating Curve= 0 ,0
Exp/Cntr=0.3,0.1

Type RM Length L Ch R = 1 ,4182    ,469,469,469
BEGIN DESCRIPTION:
Stream0305 9.0
END DESCRIPTION:
XS GIS Cut Line= 3
      1851174.99     13925874.97        1851025.       13925575.
      1850674.99     13925174.99
#Sta/Elev= 30
  4664.6 1896.57  4700.9 1891.51  4745.6 1881.49  4829.5 1854.21  4918.9 1838.04
    4954 1834.28  5024.5 1831.69    5025 1831.19  5031.5 1831.69  5042.2 1833.24
  5049.8  1840.7    5120 1840.49  5212.6 1851.68  5269.1 1863.83  5294.8 1872.52
  5311.8 1878.15    5326 1887.13  5332.6 1888.16  5368.7 1904.53  5375.4 1905.69
  5418.1 1927.28  5432.3 1939.02  5438.9  1940.7  5446.5 1947.02  5467.4 1957.83
    5475 1964.54  5481.7 1966.61  5495.9 1979.67  5503.5 1989.36  5531.5 1996.39
#Mann= 5 ,-1 , 0
  4664.6      .1       0    4954     .07       0  5024.5     .05       0
  5031.5     .07       0  5294.8      .1       0
Bank Sta=5024.5,5031.5
XS Rating Curve= 0 ,0
Exp/Cntr=0.3,0.1

Type RM Length L Ch R = 1 ,3713    ,449,449,449
BEGIN DESCRIPTION:
Stream0305 8.0
END DESCRIPTION:
XS GIS Cut Line= 3
      1851575.01     13925725.01        1851475.       13925525.
      1851075.01     13925125.01
#Sta/Elev= 30
  4786.2  1887.5  4800.2  1885.1  4844.9 1874.41  4867.3 1867.27    4884 1858.32
  4889.6 1856.47  4906.4 1845.96    4912 1844.88  4928.8 1834.55  4956.7 1831.67
  4965.1 1828.89  4992.3 1828.68  4992.8 1828.18  4999.4 1828.68    5024 1828.91
  5038.1  1831.3  5070.9 1833.61  5078.8 1834.32  5094.7  1837.1  5108.8 1837.67
  5151.2 1837.47  5306.8 1840.76  5377.5 1843.45  5402.7 1845.58  5434.1 1848.99
  5476.5 1863.26  5504.8 1874.81  5561.4 1894.53    5572 1900.48  5575.5 1900.48
#Mann= 7 ,-1 , 0
  4786.2     .07       0    4884      .1       0  4992.3     .05       0
  4999.4      .1       0  5070.9     .07       0  5078.8    .035       0
  5402.7      .1       0
Bank Sta=4992.3,4999.4
XS Rating Curve= 0 ,0
Exp/Cntr=0.3,0.1

Type RM Length L Ch R = 1 ,3264    ,467,467,467
BEGIN DESCRIPTION:
Stream0305 7.0
END DESCRIPTION:
XS GIS Cut Line= 3
        1851775.     13925675.01        1851825.       13925425.
        1851775.     13925175.02
#Sta/Elev= 30
  4737.4 1886.61    4740 1886.61  4757.8 1881.91  4778.2 1875.58  4788.4  1871.9
  4798.6 1866.63  4808.8 1862.96    4819 1857.48  4849.6 1846.81  4859.8 1841.29
    4870 1838.91  4900.6  1836.5  4910.8 1834.92  4945.6 1832.78  4951.6    1832
  4961.8 1824.75  4968.1 1824.19  4968.6 1823.69  4975.3 1823.69  4975.8 1824.19
  4994.9 1824.85  5002.6 1825.95    5023  1825.4  5043.4 1824.23  5063.8 1827.24
  5100.4 1830.63  5124.9  1831.7  5155.5  1835.4  5175.9 1836.56  5247.3 1838.28
#Mann= 5 ,-1 , 0
  4737.4      .1       0  4945.6     .07       0  4968.1     .05       0
  4975.8     .07       0  5100.4    .035       0
Bank Sta=4968.1,4975.8
XS Rating Curve= 0 ,0
Exp/Cntr=0.3,0.1

Type RM Length L Ch R = 1 ,2797    ,469,469,469
BEGIN DESCRIPTION:
Stream0305 6.0
END DESCRIPTION:
XS GIS Cut Line= 3
      1852325.01     13925625.04        1852225.       13925225.
      1852074.98     13924824.96
#Sta/Elev= 30
  4583.1 1877.56  4601.2 1873.28  4606.3  1873.7  4642.4 1861.59  4647.6 1861.42
  4677.8 1852.24  4688.8 1850.99  4706.8 1841.16  4717.1 1839.38  4807.3 1834.71
  4848.6 1828.05    4895 1825.97  4972.3 1818.31    4989 1818.11  4989.5 1817.61
  4996.8 1818.11  5087.8 1829.23  5219.7 1831.06  5246.5 1835.22  5261.6 1839.83
  5273.1 1840.56  5297.2 1849.89  5322.1 1862.28  5327.4 1862.76    5347 1872.15
  5352.3 1872.51  5377.3 1885.43  5382.6  1885.5  5407.5    1899  5422.7 1903.93
#Mann= 6 ,-1 , 0
  4583.1      .1       0  4677.8     .07       0    4989     .05       0
  4996.8     .07       0  5087.8    .035       0  5246.5      .1       0
Bank Sta=4989,4996.8
XS Rating Curve= 0 ,0
Exp/Cntr=0.3,0.1

Type RM Length L Ch R = 1 ,2328    ,442,442,442
BEGIN DESCRIPTION:
Stream0305 5.0
END DESCRIPTION:
XS GIS Cut Line= 3
        1852625.     13925124.95        1852625.       13925025.
      1852875.02     13924674.97
#Sta/Elev= 30
  4900.1 1828.93  4970.1 1826.94  4980.1 1822.67  4987.2 1816.97  4990.1 1814.64
  4997.6 1812.35  5009.6 1810.74  5010.1 1810.24  5017.5 1810.74  5022.2 1812.63
  5028.3 1811.73  5057.8 1813.98  5114.3 1812.65  5143.8 1814.74  5164.7 1813.36
  5181.3 1817.92  5200.4 1817.68  5221.3 1820.92  5244.6 1834.29  5250.7 1835.03
  5265.5 1848.54  5271.6 1864.39  5276.6 1873.55  5280.2 1882.71  5315.9  1909.6
  5351.5 1930.56  5357.7  1935.6    5381 1948.27  5393.3 1957.75  5430.2 1958.88
#Mann= 5 ,-1 , 0
  4900.1      .1       0  4987.2    .035       0  5009.6    .035       0
  5017.5    .035       0  5181.3      .1       0
Bank Sta=5009.6,5017.5
XS Rating Curve= 0 ,0
Exp/Cntr=0.3,0.1

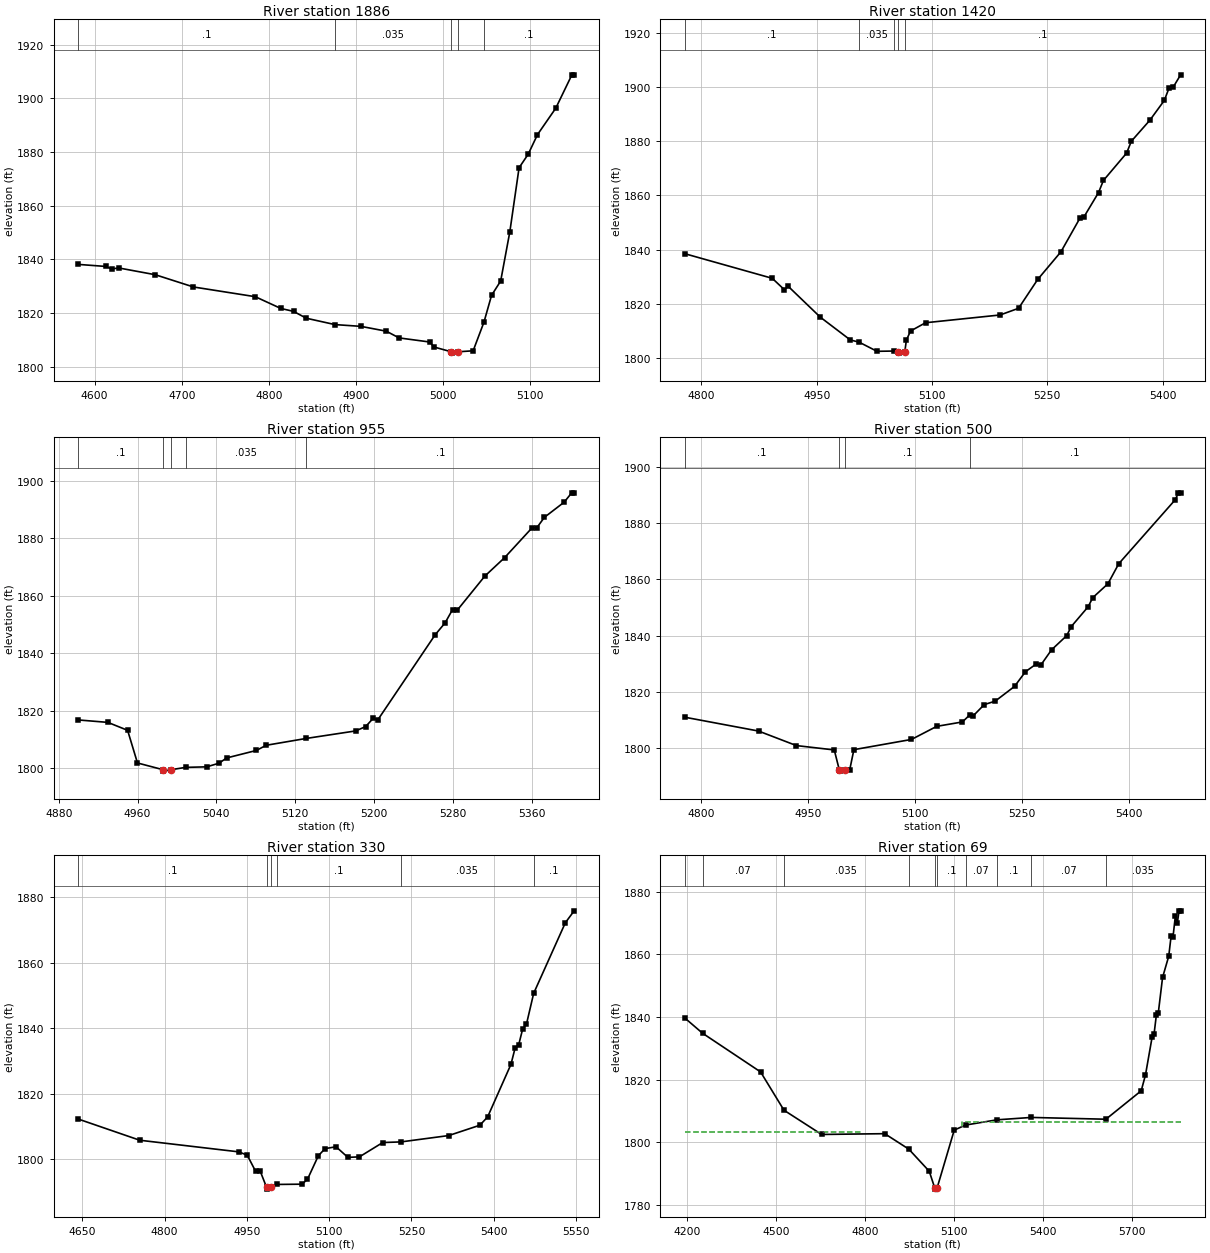
Type RM Length L Ch R = 1 ,1886    ,466,466,466
BEGIN DESCRIPTION:
Stream0305 4.0
END DESCRIPTION:
XS GIS Cut Line= 3
      1852644.54     13925319.05        1852975.       13925075.
      1853024.99     13924925.03
#Sta/Elev= 30
  4581.4 1838.14  4613.3 1837.37  4619.5 1836.45  4627.9 1836.81  4669.6  1834.3
  4713.5 1829.73  4784.4 1826.11  4813.7 1821.73  4828.3 1820.64    4843 1818.08
  4875.9 1815.71  4905.5 1815.06  4934.8 1813.25  4949.4 1810.75  4984.9 1809.21
  4989.1  1807.4  5009.3 1805.58  5009.8 1805.08  5017.2 1805.58  5034.4 1805.95
  5046.8 1816.62  5055.5 1826.59    5066 1831.96  5076.5 1850.32  5087.1 1874.16
  5097.6 1879.22  5108.2 1886.49  5129.2 1896.35  5147.7 1908.78  5150.3 1908.78
#Mann= 5 ,-1 , 0
  4581.4      .1       0  4875.9    .035       0  5009.3    .035       0
  5017.2    .035       0  5046.8      .1       0
Bank Sta=5009.3,5017.2
XS Rating Curve= 0 ,0
Exp/Cntr=0.3,0.1

Type RM Length L Ch R = 1 ,1420    ,465,465,465
BEGIN DESCRIPTION:
Stream0305 3.0
END DESCRIPTION:
XS GIS Cut Line= 3
      1853113.32     13925634.12        1853175.       13925425.
      1853324.99     13925025.02
#Sta/Elev= 30
  4778.3 1838.52  4892.1 1829.45  4907.8 1825.27    4913 1826.46  4954.6 1815.14
  4993.7 1806.73    5005 1805.94  5028.4 1802.55  5050.5 1802.65  5056.3 1802.38
  5056.8 1801.88  5064.6 1802.38  5066.6 1806.63    5072 1810.02  5091.6 1813.08
  5188.6 1815.94  5212.6  1818.4  5237.5 1829.03  5267.8 1839.24  5292.7 1851.74
    5298 1852.22  5316.7 1861.06    5323  1865.5  5353.2  1875.6  5359.4 1879.98
  5383.5 1887.72  5402.2 1894.98  5408.4 1899.54  5413.7 1899.84  5423.5 1904.44
#Mann= 5 ,-1 , 0
  4778.3      .1       0    5005    .035       0  5050.5      .1       0
  5056.3     .05       0  5064.6      .1       0
Bank Sta=5056.3,5064.6
XS Rating Curve= 0 ,0
Exp/Cntr=0.3,0.1

Type RM Length L Ch R = 1 ,955     ,455,455,455
BEGIN DESCRIPTION:
Stream0305 2.0
END DESCRIPTION:
XS GIS Cut Line= 3
        1853625.     13925575.01        1853625.       13925475.
        1853675.     13925075.03
#Sta/Elev= 30
  4899.9 1816.83  4929.9 1815.98  4949.9 1813.22  4959.9 1801.86  4985.8 1799.52
  4986.3 1799.02  4994.1 1799.52  5008.8 1800.33  5030.1 1800.51  5042.7 1801.78
  5050.3  1803.6  5080.5 1806.21  5090.6 1808.02  5131.4 1810.41  5181.3 1813.01
  5191.4 1814.52    5199 1817.36    5204 1816.97  5261.9 1846.44    5272  1850.6
  5279.6 1855.23  5284.6 1855.12  5312.3 1866.86  5332.5 1873.33  5360.2 1883.66
  5365.2 1883.76  5372.8 1887.34  5392.9 1892.63  5400.5 1895.87    5403 1895.87
#Mann= 5 ,-1 , 0
  4899.9      .1       0  4985.8     .05       0  4994.1      .1       0
  5008.8    .035       0  5131.4      .1       0
Bank Sta=4985.8,4994.1
XS Rating Curve= 0 ,0
Exp/Cntr=0.3,0.1

Type RM Length L Ch R = 1 ,500     ,170,170,170
BEGIN DESCRIPTION:
Stream0305 1.0
END DESCRIPTION:
XS GIS Cut Line= 3
      1853925.01     13925674.98        1854025.       13925475.
      1853774.99     13925074.99
#Sta/Elev= 30
  4776.8 1811.07  4880.2 1806.16  4933.3    1801  4986.4 1799.45  4993.4 1792.43
  4993.9 1791.93  5001.8 1792.43  5008.1 1792.43  5013.9 1799.55  5094.7 1803.18
  5130.1 1807.83  5166.1 1809.39  5176.5 1811.91  5181.4  1811.6  5196.7 1815.54
  5212.1 1816.78  5239.2 1822.01  5254.5 1827.22  5269.8    1830  5275.7 1829.46
  5291.1 1834.99  5312.3 1840.02  5318.8 1843.27  5342.4 1850.28  5348.9 1853.52
  5370.1 1858.43  5385.4 1865.58  5464.4 1888.23  5469.1 1890.73  5472.1 1890.73
#Mann= 4 ,-1 , 0
  4776.8      .1       0  4993.4     .05       0  5001.8      .1       0
  5176.5      .1       0
Bank Sta=4993.4,5001.8
XS Rating Curve= 0 ,0
Exp/Cntr=0.3,0.1

Type RM Length L Ch R = 1 ,330     ,261,261,261
BEGIN DESCRIPTION:
Stream0305 0.0
END DESCRIPTION:
XS GIS Cut Line= 4
      1854013.24     13925779.07      1854193.27      13925500.8
      1854200.87      13925370.8      1853876.39     13925070.88
#Sta/Elev= 30
  4642.9 1812.29  4754.9 1805.83  4935.5 1802.28  4950.7 1801.26  4965.8 1796.39
  4974.3 1796.41    4986 1791.41  4986.5 1790.91  4994.4 1791.41  5004.3 1792.34
  5050.3 1792.42  5060.3 1793.86  5080.3 1801.11  5092.5 1803.27  5112.5 1803.84
  5134.1  1800.6  5155.1 1800.76  5197.6 1805.13  5230.7 1805.32  5317.8 1807.26
  5374.5 1810.41  5388.7 1812.94  5431.2 1828.98  5438.6 1833.85  5445.4 1835.01
  5452.7 1839.88  5459.5 1841.26  5472.6 1850.66  5530.4 1872.23  5546.4 1875.85
#Mann= 6 ,-1 , 0
  4642.9      .1       0    4986     .05       0  4994.4      .1       0
  5004.3      .1       0  5230.7    .035       0  5472.6      .1       0
#XS Ineff= 2 , 0
                          5103.5         1803.55
Permanent Ineff=
       F       F
Bank Sta=4986,4994.4
XS Rating Curve= 0 ,0
Exp/Cntr=0.3,0.1

Type RM Length L Ch R = 1 ,69      ,0,0,0
BEGIN DESCRIPTION:
Stream0305 0.1
END DESCRIPTION:
XS GIS Cut Line= 5
      1853895.77     13926126.28      1854395.78     13925560.29
      1854427.03     13925452.65      1854333.28     13925197.44
      1853921.83     13924862.38
#Sta/Elev= 30
  4192.6 1839.66  4252.3 1834.81  4447.8 1822.46  4526.6 1810.24  4653.4 1802.51
  4865.9 1802.76  4946.9 1797.83  5015.8 1790.78  5033.9 1785.57  5034.4 1785.07
  5042.7 1785.57    5100  1803.9    5138 1805.51    5244 1807.18  5359.7 1807.94
  5610.8 1807.37  5729.7 1816.45  5744.1 1821.52  5766.4 1833.58  5772.8 1834.41
  5780.7 1840.63  5787.2 1841.27  5801.6 1852.59  5822.4 1859.39  5830.3 1865.79
  5836.7 1865.46  5844.7 1872.22  5851.1 1869.85  5857.1 1873.85  5862.4 1873.85
#Mann= 10 ,-1 , 0
  4192.6    .035       0  4252.3     .07       0  4526.6    .035       0
  4946.9      .1       0  5033.9     .05       0  5042.7      .1       0
    5138     .07       0    5244      .1       0  5359.7     .07       0
  5610.8    .035       0
#XS Ineff= 2 , 0
         4785.21 1803.15 5126.87         1806.35
Permanent Ineff=
       F       F
Bank Sta=5033.9,5042.7
XS Rating Curve= 0 ,0
Exp/Cntr=0.3,0.1

Chan Stop Cuts=-1
Use User Specified Reach Order=0
Composite Channel Slope=5