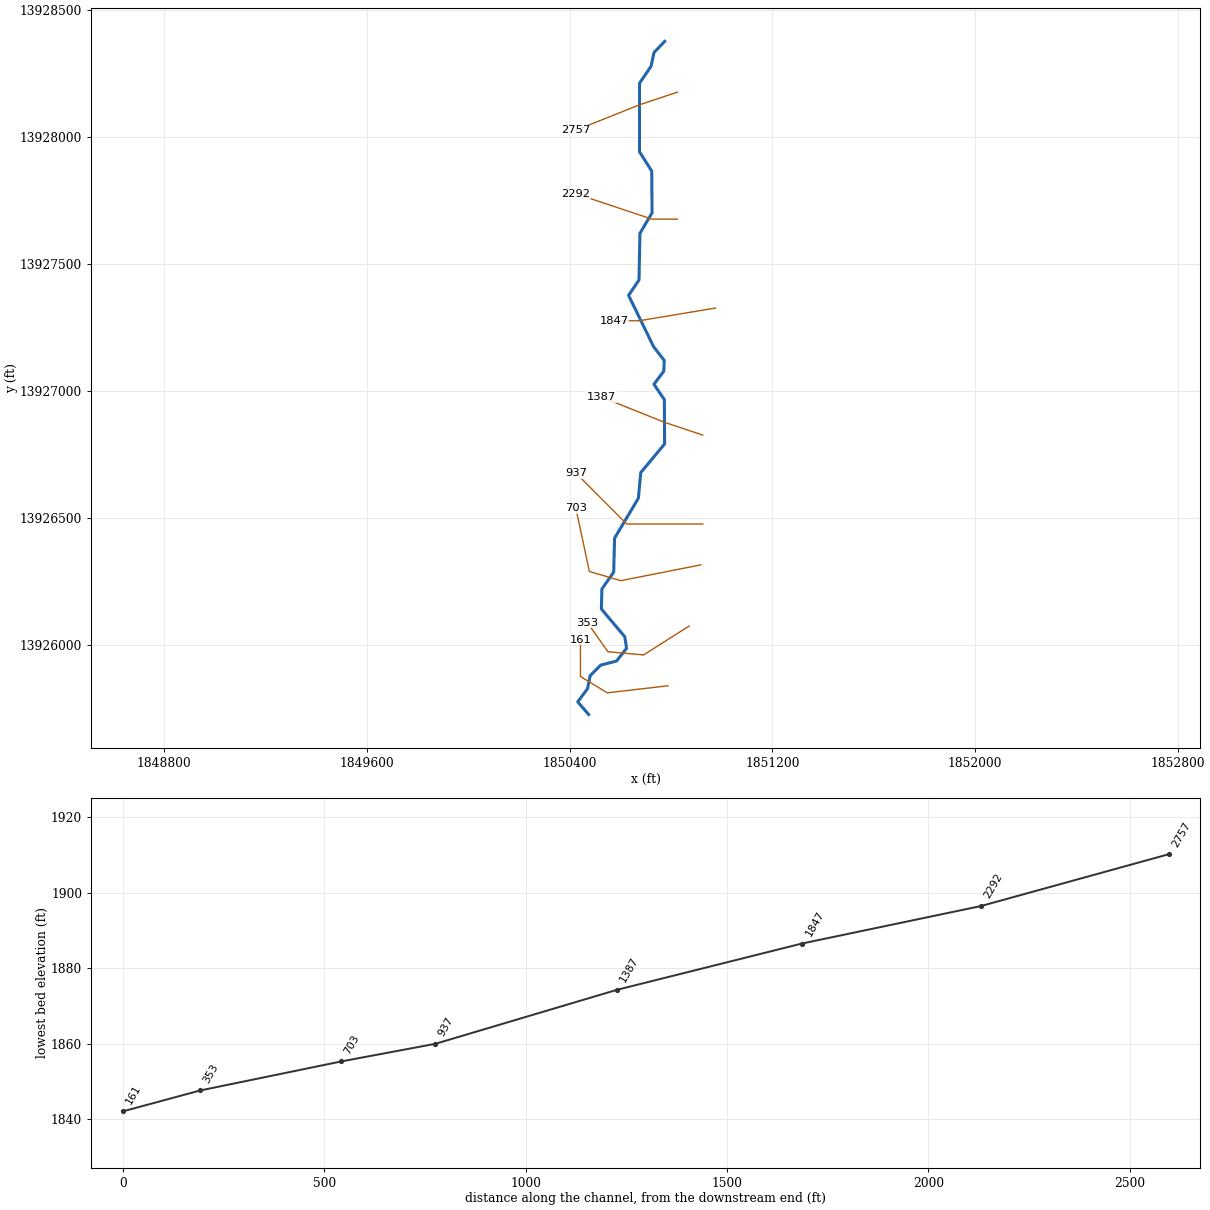
--- Stream0306.prj (project) ---

Proj Title=Stream0306 Base Level Engineering
Current Plan=p01
Default Exp/Contr=0.3,0.1
English Units
Geom File=g01
Flow File=f01
Plan File=p01
Y Axis Title=Elevation
X Axis Title(PF)=Main Channel Distance
X Axis Title(XS)=Station
BEGIN DESCRIPTION:
Stream0306
END DESCRIPTION:
DSS Export Rating Curves= 0
DSS Export Rating Curve Sorted= 0
DSS Export Volume Flow Curves= 0
DXF OffsetX= 0
DXF OffsetY= 0
DXF ScaleX= 1
DXF ScaleY= 10

--- Stream0306.p01 (plan) ---

Plan Title=Multiple Run
Short Identifier=Multiple
Geom File=g01
Flow File=f01
Subcritical Flow
K Sum by GR= 0
Std Step Tol= 0.01
Critical Tol= 0.01
Num of Std Step Trials= 20
Max Error Tol= 0.3
Flow Tol Ratio= 0.001
Split Flow NTrial= 30
Split Flow Tol= 0.02
Split Flow Ratio= 0.02
Log Output Level= 0
Friction Slope Method= 1
Unsteady Friction Slope Method= 2
Unsteady Bridges Friction Slope Method= 1
Parabolic Critical Depth
Global Vel Dist=  1 , 1 , 1
Global Log Level= 0
CheckData=True
Encroach Param= -1, 0, 0, 0
BEGIN DESCRIPTION:
Multiple Run
END DESCRIPTION:

--- Stream0306.f01 (steady flow) ---

Flow Title=Multiple
Program Version=4.10
Number of Profiles= 7
Profile Names=10-year,25-year,50-year,1pct_min,100-year,1pct_plu,500-year
River Rch & RM=Stream0306,Reach-1         ,2757
     530     874    1193     791    1578    3149    2720
Boundary for River Rch & Prof#=Stream0306,Reach-1         , 1
Up Type= 0
Dn Type= 3
Dn Slope=0.02
Boundary for River Rch & Prof#=Stream0306,Reach-1         , 2
Up Type= 0
Dn Type= 3
Dn Slope=0.02
Boundary for River Rch & Prof#=Stream0306,Reach-1         , 3
Up Type= 0
Dn Type= 3
Dn Slope=0.02
Boundary for River Rch & Prof#=Stream0306,Reach-1         , 4
Up Type= 0
Dn Type= 3
Dn Slope=0.02
Boundary for River Rch & Prof#=Stream0306,Reach-1         , 5
Up Type= 0
Dn Type= 3
Dn Slope=0.02
Boundary for River Rch & Prof#=Stream0306,Reach-1         , 6
Up Type= 0
Dn Type= 3
Dn Slope=0.02
Boundary for River Rch & Prof#=Stream0306,Reach-1         , 7
Up Type= 0
Dn Type= 3
Dn Slope=0.02
DSS Import GetInterval= 0
DSS Import GetPeak= 0
DSS Import FillOption= 0

--- Stream0306.g01 (geometry) ---

Geom Title=Existing Conditions
Program Version=4.10

River Reach=Stream0306      ,Reach-1
Reach XY= 30
        1850775.       13928375.      1850732.91     13928331.15
      1850720.92     13928276.69       1850675.5     13928209.79
      1850675.52     13927940.22      1850723.78     13927864.49
       1850725.2     13927699.92      1850677.26     13927619.06
      1850673.62     13927435.44      1850632.53     13927374.99
      1850731.16      13927172.8      1850773.16     13927118.88
       1850771.4     13927076.64      1850732.59     13927025.01
      1850773.62     13926964.56      1850774.61     13926790.16
      1850680.54     13926677.42      1850671.17     13926576.59
      1850577.25     13926419.07      1850573.77     13926285.51
      1850527.16     13926219.02      1850525.25     13926140.22
      1850617.53     13926031.02      1850624.51     13925985.49
       1850585.1     13925935.65      1850522.49     13925919.24
       1850480.7     13925877.54      1850470.63     13925826.67
      1850431.87     13925774.88        1850475.       13925725.

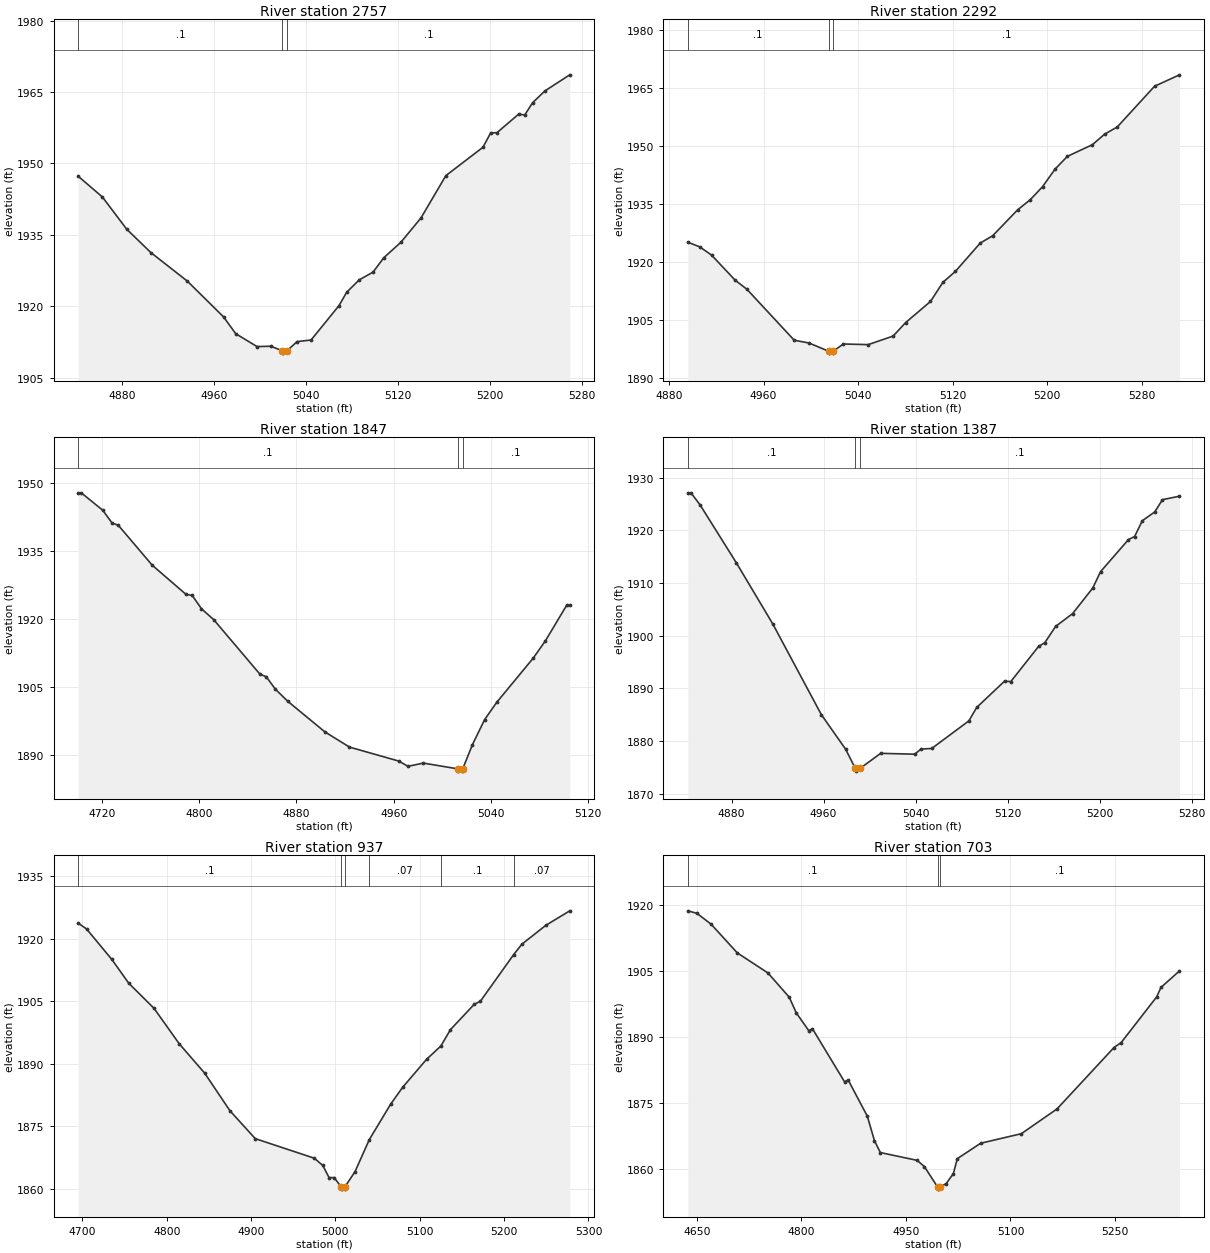
Type RM Length L Ch R = 1 ,2757    ,465,465,465
BEGIN DESCRIPTION:
Stream0306 6.0
END DESCRIPTION:
XS GIS Cut Line= 3
      1850824.99       13928175.        1850675.       13928125.
      1850424.97     13928024.99
#Sta/Elev= 30
  4841.8 1947.33  4862.9 1942.97    4884 1936.22    4905 1931.31  4936.7 1925.32
  4968.3 1917.79  4978.8 1914.28  4997.3 1911.58  5009.3 1911.64  5019.4  1910.7
  5019.7  1910.2  5023.4  1910.7  5032.2 1912.62  5044.3 1912.95  5068.6 1920.17
  5075.3 1922.98  5086.1 1925.56  5098.2  1927.2  5107.6 1930.23  5122.4 1933.46
  5139.9 1938.58  5161.5 1947.44  5193.8 1953.41  5200.5 1956.44  5205.9 1956.45
  5224.7 1960.33  5230.1 1960.18  5236.9 1962.74  5247.6 1965.22  5269.2  1968.6
#Mann= 3 ,-1 , 0
  4841.8      .1       0  5019.4     .05       0  5023.4      .1       0
Bank Sta=5019.4,5023.4
XS Rating Curve= 0 ,0
Exp/Cntr=0.3,0.1

Type RM Length L Ch R = 1 ,2292    ,445,445,445
BEGIN DESCRIPTION:
Stream0306 5.0
END DESCRIPTION:
XS GIS Cut Line= 3
      1850824.98       13927675.        1850725.       13927675.
        1850425.       13927775.
#Sta/Elev= 30
  4895.9 1925.17  4905.9 1923.97  4915.9 1921.85  4935.9 1915.36  4945.9    1913
  4985.9 1899.84  4998.5 1899.11    5015    1897  5015.2  1896.5  5018.7  1896.5
    5019    1897  5027.5 1898.86  5048.6  1898.7  5069.7 1900.91  5080.2 1904.38
  5101.3 1909.85  5111.8 1914.79  5122.4 1917.63  5143.4 1924.94    5154 1926.85
  5175.1 1933.55  5185.6  1936.1  5196.2 1939.53  5206.7 1944.04  5217.2 1947.36
  5238.3 1950.36  5248.9 1953.13  5259.4 1954.95    5291 1965.48  5312.1 1968.43
#Mann= 3 ,-1 , 0
  4895.9      .1       0    5015     .05       0    5019      .1       0
Bank Sta=5015,5019
XS Rating Curve= 0 ,0
Exp/Cntr=0.3,0.1

Type RM Length L Ch R = 1 ,1847    ,460,460,460
BEGIN DESCRIPTION:
Stream0306 4.0
END DESCRIPTION:
XS GIS Cut Line= 3
      1850975.03       13927325.        1850675.       13927275.
      1850574.97       13927275.
#Sta/Elev= 30
  4700.5 1947.91  4703.1 1947.91  4720.8 1944.06  4728.4 1941.25  4733.5 1940.77
  4761.4 1931.96  4789.2 1925.52  4794.3 1925.29  4801.9 1922.35    4812 1919.94
  4850.1 1907.89  4855.1 1907.39  4862.7 1904.61  4872.9 1901.94  4903.3 1895.22
  4923.6 1891.85  4964.1 1888.77  4971.7 1887.61  4984.4 1888.32  5012.7 1887.05
  5012.9 1886.55  5016.4 1886.55  5016.7 1887.05  5024.7 1892.38  5034.7  1897.9
  5044.7 1901.73  5074.7 1911.47  5084.7 1915.28  5102.2 1923.13  5104.7 1923.13
#Mann= 3 ,-1 , 0
  4700.5      .1       0  5012.7     .05       0  5016.7      .1       0
Bank Sta=5012.7,5016.7
XS Rating Curve= 0 ,0
Exp/Cntr=0.3,0.1

Type RM Length L Ch R = 1 ,1387    ,450,450,450
BEGIN DESCRIPTION:
Stream0306 3.0
END DESCRIPTION:
XS GIS Cut Line= 3
      1850925.04     13926824.99        1850775.       13926875.
      1850525.02     13926974.99
#Sta/Elev= 30
    4842 1927.15  4844.7 1927.15  4852.6 1924.86  4884.2 1913.83  4915.8 1902.24
    4958 1885.01  4979.1 1878.44  4987.6 1874.76  4987.9 1874.26  4991.6 1874.76
  5009.6 1877.64  5039.2 1877.48  5044.6 1878.44    5054 1878.57  5086.3 1883.81
  5093.1 1886.36  5117.3 1891.36  5122.7 1891.27  5146.9 1897.96  5152.3 1898.67
  5161.7 1901.76  5176.5  1904.2    5194 1909.06  5200.8 1912.17    5225 1918.26
  5230.4 1918.85  5237.1 1921.85  5247.9 1923.52  5254.6 1925.85  5269.4 1926.51
#Mann= 3 ,-1 , 0
    4842      .1       0  4987.6     .05       0  4991.6      .1       0
Bank Sta=4987.6,4991.6
XS Rating Curve= 0 ,0
Exp/Cntr=0.3,0.1

Type RM Length L Ch R = 1 ,937     ,234,234,234
BEGIN DESCRIPTION:
Stream0306 2.0
END DESCRIPTION:
XS GIS Cut Line= 3
      1850924.96       13926475.        1850625.       13926475.
        1850425.       13926675.
#Sta/Elev= 30
    4695 1923.74    4705 1922.34    4735 1915.02    4755 1909.33    4785 1903.31
    4815 1894.78    4845 1887.79    4875 1878.76    4905 1872.08    4975 1867.39
    4985 1865.66  4992.5 1862.74  4998.5 1862.74  5007.1 1860.48  5007.3 1859.98
  5010.8 1859.98  5011.1 1860.48  5023.2 1864.14  5040.2 1871.85  5065.7  1880.4
  5079.8 1884.41  5108.1  1891.1    5125 1894.27  5136.4 1898.21  5164.7  1904.3
  5171.7 1904.96  5211.4 1916.21  5221.2 1918.71  5249.5 1923.21  5277.8 1926.68
#Mann= 6 ,-1 , 0
    4695      .1       0  5007.1     .05       0  5011.1      .1       0
  5040.2     .07       0    5125      .1       0  5211.4     .07       0
Bank Sta=5007.1,5011.1
XS Rating Curve= 0 ,0
Exp/Cntr=0.3,0.1

Type RM Length L Ch R = 1 ,703     ,350,350,350
BEGIN DESCRIPTION:
Stream0306 1.0
END DESCRIPTION:
XS GIS Cut Line= 4
      1850917.76      13926314.1      1850601.63     13926251.79
      1850477.91       13926288.      1850424.62     13926536.94
#Sta/Elev= 30
  4636.9 1918.76  4649.9 1918.19  4670.3  1915.7  4707.9 1909.16  4751.8  1904.6
  4782.4 1899.07  4792.6 1895.47  4810.6  1891.4  4815.7 1891.88  4861.9 1879.75
    4867 1880.18  4894.5 1871.93  4904.7 1866.35  4913.2 1863.64    4966 1861.86
  4976.4 1860.44  4995.3  1855.8  4995.5  1855.3  4999.3  1855.8  5007.7 1856.57
  5018.1 1858.86  5023.6 1862.24  5057.1 1865.76  5115.6 1867.94  5166.8 1873.59
  5248.6 1887.59  5258.8  1888.7  5309.9 1899.15    5316 1901.29  5342.6 1905.06
#Mann= 3 ,-1 , 0
  4636.9      .1       0  4995.3     .05       0  4999.3      .1       0
Bank Sta=4995.3,4999.3
XS Rating Curve= 0 ,0
Exp/Cntr=0.3,0.1

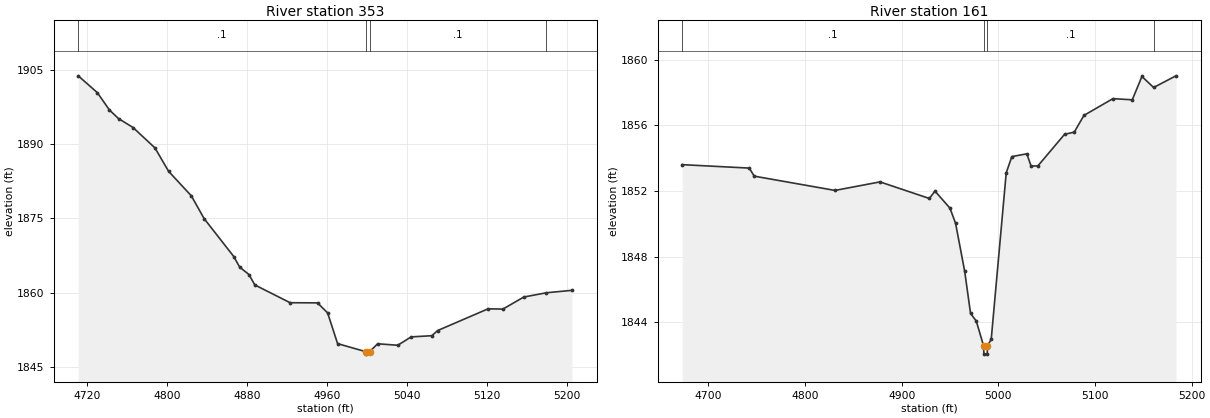
Type RM Length L Ch R = 1 ,353     ,192,192,192
BEGIN DESCRIPTION:
Stream0306 0.0
END DESCRIPTION:
XS GIS Cut Line= 4
      1850871.34      13926073.3      1850691.99     13925959.66
      1850551.05     13925971.94      1850470.26     13926086.41
#Sta/Elev= 30
  4711.3  1903.8  4730.4 1900.41  4742.5 1896.91  4751.6 1895.17  4766.2 1893.36
  4788.1 1889.24  4801.7 1884.53  4824.5 1879.56  4837.2 1874.99  4866.9 1867.32
  4872.8 1865.19  4882.1 1863.68    4888 1861.58  4923.3 1857.99  4950.7 1857.96
  4960.8 1855.94  4970.8 1849.73  4998.9 1848.11  4999.2 1847.61  5002.9 1848.11
  5010.9  1849.7    5031  1849.4  5044.4 1851.09  5065.1 1851.33  5070.9 1852.37
  5121.4 1856.76  5136.2  1856.7  5157.1 1859.14  5179.8    1860  5205.2 1860.49
#Mann= 4 ,-1 , 0
  4711.3      .1       0  4998.9     .05       0  5002.9      .1       0
  5179.8     .07       0
Bank Sta=4998.9,5002.9
XS Rating Curve= 0 ,0
Exp/Cntr=0.3,0.1

Type RM Length L Ch R = 1 ,161     ,0,0,0
BEGIN DESCRIPTION:
Stream0306 0.3
END DESCRIPTION:
XS GIS Cut Line= 4
      1850788.14     13925838.07      1850548.56     13925810.29
      1850442.66     13925874.53      1850442.66     13926020.18
#Sta/Elev= 30
    4673 1853.61  4742.3  1853.4  4747.4 1852.91    4831 1852.04  4877.5 1852.56
  4928.6 1851.55  4934.4    1852  4949.9 1850.96  4955.7 1850.04  4965.1 1847.13
  4971.2 1844.55  4977.1 1844.09  4984.7 1842.57    4985 1842.07  4988.5 1842.07
  4988.7 1842.57  4992.6 1842.98  5008.1 1853.11  5013.9  1854.1  5029.4 1854.27
  5033.8 1853.53  5040.8 1853.53  5068.5 1855.46  5078.5 1855.59  5088.5 1856.61
  5118.5 1857.63  5138.5 1857.56  5148.5 1858.98  5160.6 1858.31  5183.7 1859.02
#Mann= 4 ,-1 , 0
    4673      .1       0  4984.7     .05       0  4988.7      .1       0
  5160.6     .07       0
Bank Sta=4984.7,4988.7
XS Rating Curve= 0 ,0
Exp/Cntr=0.3,0.1

Chan Stop Cuts=-1
Use User Specified Reach Order=0
Composite Channel Slope=5