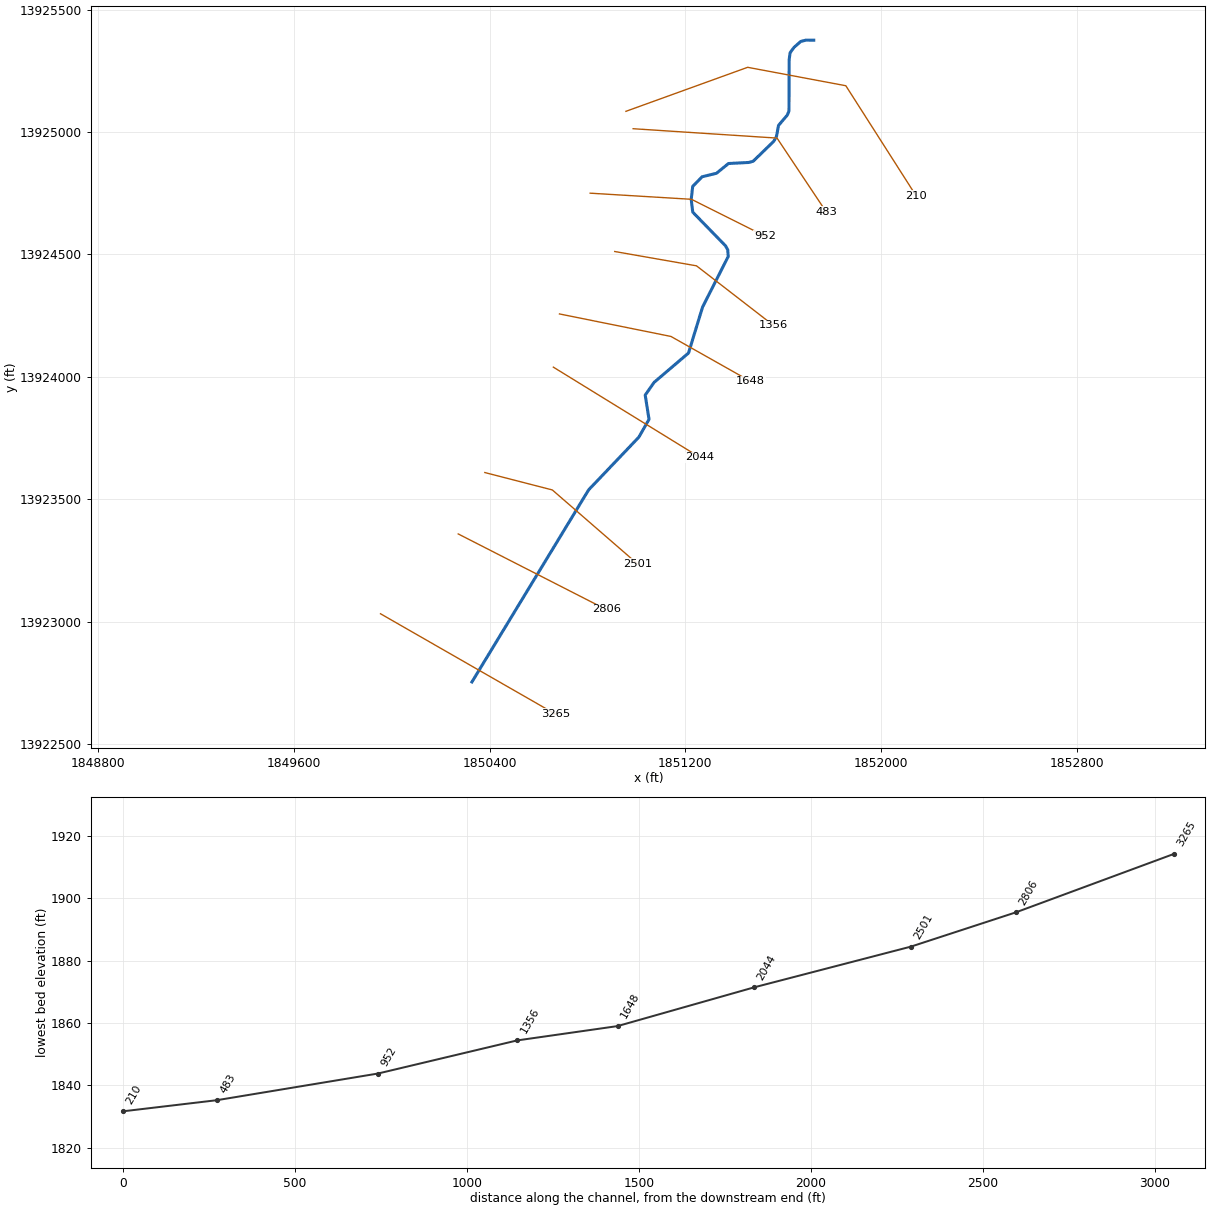
--- Stream0307.prj (project) ---

Proj Title=Stream0307 Base Level Engineering
Current Plan=p01
Default Exp/Contr=0.3,0.1
English Units
Geom File=g01
Flow File=f01
Plan File=p01
Y Axis Title=Elevation
X Axis Title(PF)=Main Channel Distance
X Axis Title(XS)=Station
BEGIN DESCRIPTION:
Stream0307
END DESCRIPTION:
DSS Export Rating Curves= 0
DSS Export Rating Curve Sorted= 0
DSS Export Volume Flow Curves= 0
DXF OffsetX= 0
DXF OffsetY= 0
DXF ScaleX= 1
DXF ScaleY= 10

--- Stream0307.p01 (plan) ---

Plan Title=Multiple Run
Short Identifier=Multiple
Geom File=g01
Flow File=f01
Subcritical Flow
K Sum by GR= 0
Std Step Tol= 0.01
Critical Tol= 0.01
Num of Std Step Trials= 20
Max Error Tol= 0.3
Flow Tol Ratio= 0.001
Split Flow NTrial= 30
Split Flow Tol= 0.02
Split Flow Ratio= 0.02
Log Output Level= 0
Friction Slope Method= 1
Unsteady Friction Slope Method= 2
Unsteady Bridges Friction Slope Method= 1
Parabolic Critical Depth
Global Vel Dist=  1 , 1 , 1
Global Log Level= 0
CheckData=True
Encroach Param= -1, 0, 0, 0
BEGIN DESCRIPTION:
Multiple Run
END DESCRIPTION:

--- Stream0307.f01 (steady flow) ---

Flow Title=Multiple
Program Version=4.10
Number of Profiles= 7
Profile Names=10-year,25-year,50-year,1pct_min,100-year,1pct_plu,500-year
River Rch & RM=Stream0307,Reach-1         ,3265
     615    1027    1412     943    1881    3753    3289
Boundary for River Rch & Prof#=Stream0307,Reach-1         , 1
Up Type= 0
Dn Type= 3
Dn Slope=0.018
Boundary for River Rch & Prof#=Stream0307,Reach-1         , 2
Up Type= 0
Dn Type= 3
Dn Slope=0.018
Boundary for River Rch & Prof#=Stream0307,Reach-1         , 3
Up Type= 0
Dn Type= 3
Dn Slope=0.018
Boundary for River Rch & Prof#=Stream0307,Reach-1         , 4
Up Type= 0
Dn Type= 3
Dn Slope=0.018
Boundary for River Rch & Prof#=Stream0307,Reach-1         , 5
Up Type= 0
Dn Type= 3
Dn Slope=0.018
Boundary for River Rch & Prof#=Stream0307,Reach-1         , 6
Up Type= 0
Dn Type= 3
Dn Slope=0.018
Boundary for River Rch & Prof#=Stream0307,Reach-1         , 7
Up Type= 0
Dn Type= 3
Dn Slope=0.018
DSS Import GetInterval= 0
DSS Import GetPeak= 0
DSS Import FillOption= 0

--- Stream0307.g01 (geometry) ---

Geom Title=Existing Conditions
Program Version=4.10

River Reach=Stream0307      ,Reach-1
Reach XY= 30
      1850327.71     13922753.21      1850804.64     13923537.76
        1851010.     13923753.21      1851051.67     13923826.12
      1851036.04     13923925.08       1851072.5     13923977.17
      1851213.13     13924096.96      1851270.42     13924284.46
      1851375.47      13924491.5      1851373.32     13924518.86
      1851364.48     13924534.79      1851230.39     13924672.58
      1851224.11     13924725.03      1851230.29     13924777.67
      1851268.61       13924817.      1851327.15     13924831.15
      1851376.58     13924871.17      1851459.79     13924875.52
      1851477.44     13924880.52      1851561.39     13924961.76
      1851572.51     13924981.02      1851581.14     13925027.17
      1851616.91     13925068.92       1851623.8      13925085.5
      1851624.55     13925295.23      1851628.37     13925323.74
      1851644.28     13925345.56      1851672.05     13925369.87
      1851692.92     13925375.16        1851725.       13925375.

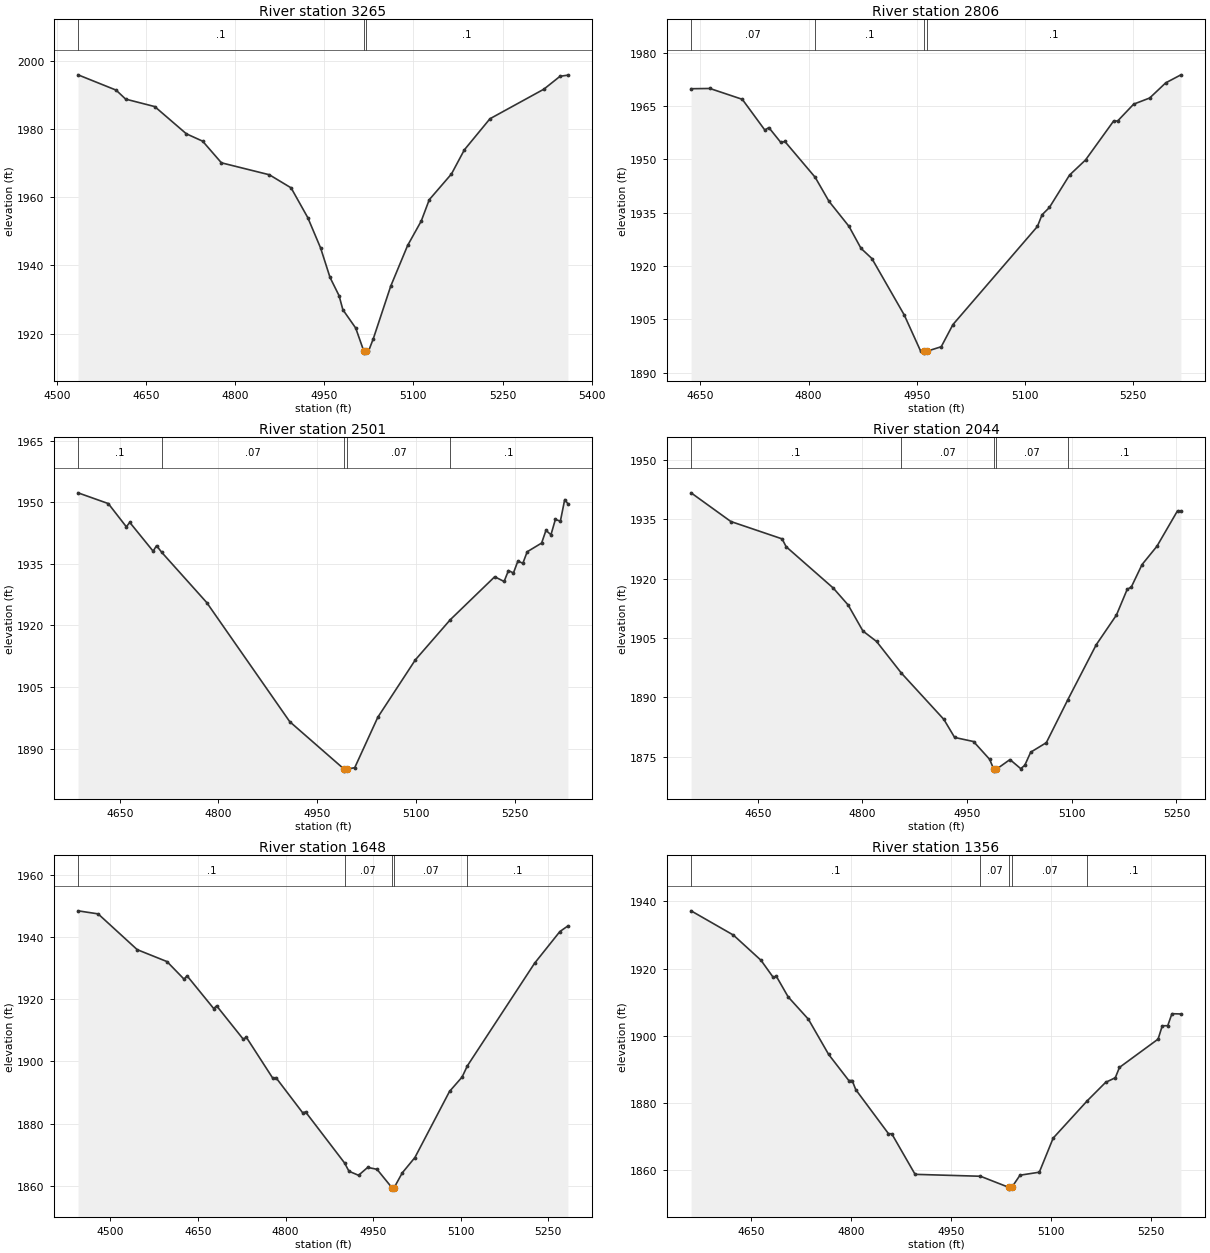
Type RM Length L Ch R = 1 ,3265    ,459,459,459
BEGIN DESCRIPTION:
Stream0307 3.0
END DESCRIPTION:
XS GIS Cut Line= 2
      1849954.01     13923031.81      1850668.93     13922622.09
#Sta/Elev= 30
  4535.8 1995.86  4599.8 1991.38  4615.9 1988.74  4664.8 1986.55    4718 1978.57
  4745.4 1976.41    4777 1970.06  4857.6 1966.56  4894.2 1962.72  4922.3 1953.98
  4943.9 1945.06  4959.7 1936.45  4974.9 1931.11  4981.3 1926.99  5002.9 1921.61
  5016.7 1914.76  5016.9 1914.26  5020.7 1914.76  5024.4 1914.82  5032.6 1918.54
  5061.8  1933.9  5090.2 1945.82  5113.2 1953.02  5126.6 1959.24    5164  1966.8
  5185.6 1973.85  5228.7 1982.98  5319.4 1991.65  5346.7 1995.44  5359.8 1995.76
#Mann= 3 ,-1 , 0
  4535.8      .1       0  5016.7     .05       0  5020.7      .1       0
Bank Sta=5016.7,5020.7
XS Rating Curve= 0 ,0
Exp/Cntr=0.3,0.1

Type RM Length L Ch R = 1 ,2806    ,305,305,305
BEGIN DESCRIPTION:
Mapping XS 03a56041
END DESCRIPTION:
XS GIS Cut Line= 2
      1850271.76     13923357.87      1850876.47     13923049.26
#Sta/Elev= 30
  4637.1  1969.9  4663.2 1969.97  4708.1 1966.92  4739.3 1958.28  4744.9 1958.97
  4761.5 1954.78  4767.1 1955.06  4809.1 1944.98  4828.2 1938.24    4856 1931.17
  4872.6    1925  4887.7 1922.13  4932.6 1906.23  4955.1 1896.15  4959.5 1896.02
  4959.8 1895.52  4963.5 1896.02  4983.8 1897.32    5000 1903.55  5117.1 1931.15
  5123.5 1934.43  5133.7 1936.49  5161.6  1945.6  5183.8 1949.86  5222.7 1960.81
  5228.3 1960.83  5250.5 1965.56  5272.7 1967.29  5294.9 1971.55    5316 1973.81
#Mann= 4 ,-1 , 0
  4637.1     .07       0  4809.1      .1       0  4959.5     .05       0
  4963.5      .1       0
Bank Sta=4959.5,4963.5
XS Rating Curve= 0 ,0
Exp/Cntr=0.3,0.1

Type RM Length L Ch R = 1 ,2501    ,457,457,457
BEGIN DESCRIPTION:
Mapping XS ca6ebaa3
END DESCRIPTION:
XS GIS Cut Line= 3
      1850380.42     13923608.71      1850656.38     13923537.63
      1851003.36     13923236.63
#Sta/Elev= 30
  4586.6 1952.29  4632.6 1949.67    4660 1944.02  4665.2 1945.09  4700.7 1938.08
  4705.9 1939.43    4714 1937.76  4782.1 1925.58  4908.3 1896.56  4990.8 1885.02
    4991 1884.52  4994.8 1885.02    5007 1885.35  5042.1 1897.64  5099.1 1911.61
  5152.2 1921.39  5219.7 1931.85    5234  1930.7  5240.6 1933.36  5248.2 1932.78
  5254.9 1935.66  5262.5 1935.14  5269.1 1937.94    5291 1940.06  5297.6 1943.15
  5305.2 1942.08  5311.9 1945.81  5319.5 1945.39  5326.1 1950.65  5330.9 1949.63
#Mann= 5 ,-1 , 0
  4586.6      .1       0    4714     .07       0  4990.8     .05       0
  4994.8     .07       0  5152.2      .1       0
Bank Sta=4990.8,4994.8
XS Rating Curve= 0 ,0
Exp/Cntr=0.3,0.1

Type RM Length L Ch R = 1 ,2044    ,396,396,396
BEGIN DESCRIPTION:
Mapping XS daeba45c
END DESCRIPTION:
XS GIS Cut Line= 2
      1850660.53      13924039.3       1851258.4     13923671.39
#Sta/Elev= 30
  4554.4 1941.65  4611.4 1934.41  4684.8 1930.03  4690.7 1928.04  4758.2 1917.61
  4779.5 1913.34  4800.7 1906.77  4820.2 1904.14  4855.7 1896.17  4916.7 1884.46
  4932.1 1879.91  4959.2 1878.88  4982.3 1874.38  4988.1 1871.91  4988.3 1871.41
  4992.1 1871.91  5011.4 1874.33  5026.8 1872.04  5032.6 1872.87  5041.1 1876.19
  5063.5 1878.59  5094.3 1889.43    5135  1903.3    5164 1910.81  5179.4 1917.29
  5185.3 1917.88  5200.7 1923.55    5222 1928.16  5251.5 1937.11  5256.4 1937.11
#Mann= 5 ,-1 , 0
  4554.4      .1       0  4855.7     .07       0  4988.1     .05       0
  4992.1     .07       0  5094.3      .1       0
Bank Sta=4988.1,4992.1
XS Rating Curve= 0 ,0
Exp/Cntr=0.3,0.1

Type RM Length L Ch R = 1 ,1648    ,292,292,292
BEGIN DESCRIPTION:
Mapping XS f3b279a2
END DESCRIPTION:
XS GIS Cut Line= 3
       1850685.6     13924256.68      1851141.32     13924164.71
      1851467.41     13923980.76
#Sta/Elev= 30
  4444.5 1948.38  4478.9  1947.4  4545.9 1935.91  4596.9 1932.08  4626.2 1926.43
  4631.3 1927.51  4676.9 1917.01    4682 1917.86  4727.7 1907.13  4732.8  1907.8
  4778.5 1894.53  4783.6 1894.81  4829.3 1883.55  4834.4 1883.79  4901.2  1867.4
  4908.7 1864.75  4925.1 1863.44  4940.8 1865.98  4956.8 1865.36  4982.2  1859.5
  4982.4    1859  4986.2  1859.5  5000.1 1864.24  5021.7 1869.15    5081 1890.38
  5102.6 1895.01  5111.5 1898.57  5226.8 1931.56  5270.1 1941.73  5283.8 1943.52
#Mann= 5 ,-1 , 0
  4444.5      .1       0  4901.2     .07       0  4982.2     .05       0
  4986.2     .07       0  5111.5      .1       0
Bank Sta=4982.2,4986.2
XS Rating Curve= 0 ,0
Exp/Cntr=0.3,0.1

Type RM Length L Ch R = 1 ,1356    ,404,404,404
BEGIN DESCRIPTION:
Mapping XS 3a51f20c
END DESCRIPTION:
XS GIS Cut Line= 3
      1850911.43     13924511.68      1851245.83     13924453.16
      1851559.34     13924210.72
#Sta/Elev= 30
  4559.4 1937.21    4623 1929.99  4664.5 1922.48  4682.5 1917.49  4687.6  1917.7
  4705.2 1911.61  4735.6 1904.96  4766.1 1894.46  4796.3 1886.72  4801.4 1886.72
  4806.7 1884.02  4855.8 1870.93  4860.9 1870.85  4895.9  1858.8  4994.1 1858.23
    5037  1854.9  5037.3  1854.4    5041  1854.9  5053.5 1858.54  5082.5 1859.44
  5103.3 1869.58  5154.6 1880.71  5182.1 1886.17  5196.6 1887.54  5202.9 1890.62
  5260.9 1899.04  5267.2    1903  5275.4 1903.03  5281.7  1906.6  5295.2 1906.52
#Mann= 5 ,-1 , 0
  4559.4      .1       0  4994.1     .07       0    5037     .05       0
    5041     .07       0  5154.6      .1       0
Bank Sta=5037,5041
XS Rating Curve= 0 ,0
Exp/Cntr=0.3,0.1

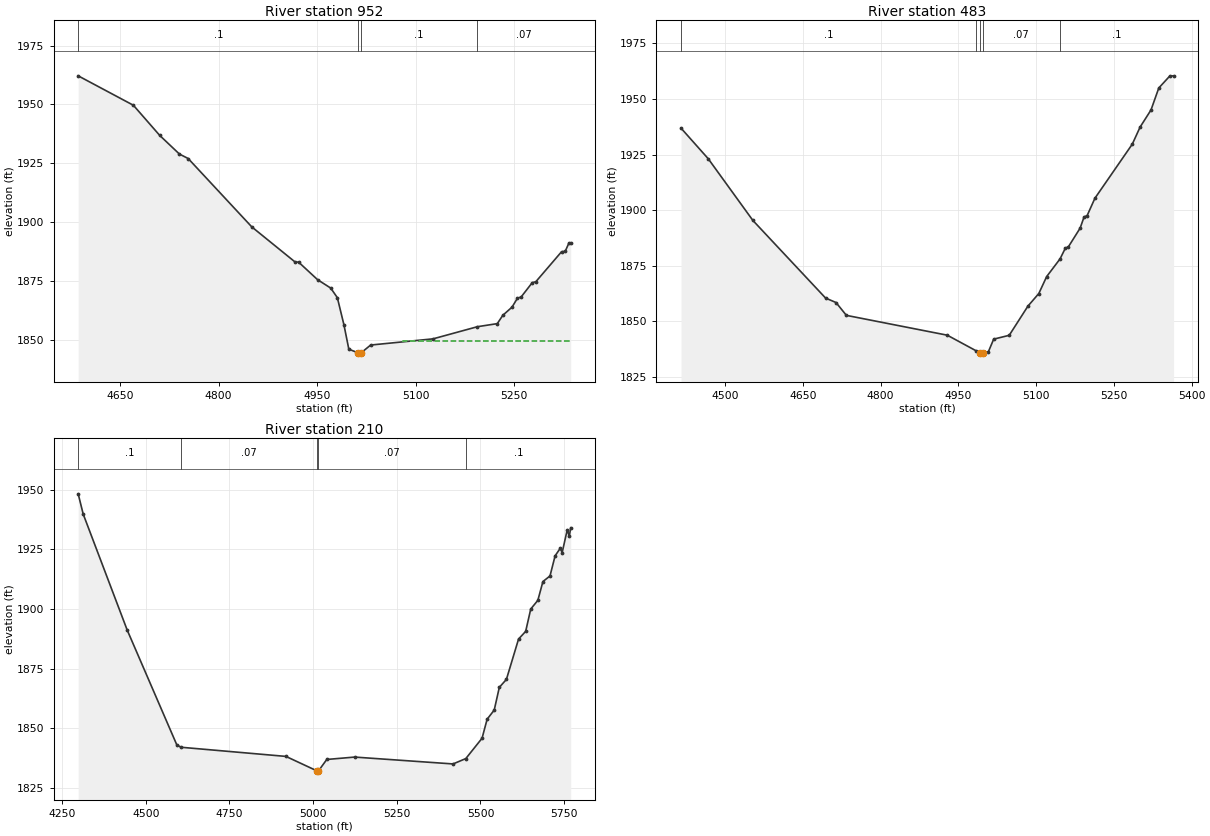
Type RM Length L Ch R = 1 ,952     ,469,469,469
BEGIN DESCRIPTION:
Stream0307 2.0
END DESCRIPTION:
XS GIS Cut Line= 3
      1850811.06     13924749.98        1851225.       13924725.
        1851525.       13924575.
#Sta/Elev= 30
  4586.2 1962.13  4670.3 1949.61  4710.4 1936.79  4740.4 1928.86  4753.7 1926.97
  4850.6 1897.89  4916.8  1882.9  4921.8 1882.93  4950.8 1875.44  4970.8 1871.87
  4980.9 1867.79  4990.9  1856.3  4998.4 1845.88  5012.9 1844.28  5013.1 1843.78
  5016.9 1844.28  5031.6 1847.64  5126.7 1850.28  5194.2 1855.44  5224.5 1856.75
  5232.9 1860.29  5246.9 1863.76  5255.2 1867.56  5260.8 1868.09  5277.6 1874.13
  5283.2 1874.58  5322.3 1887.31  5327.9 1887.48  5333.5 1890.98  5336.3 1890.98
#Mann= 4 ,-1 , 0
  4586.2      .1       0  5012.9     .05       0  5016.9      .1       0
  5194.2     .07       0
#XS Ineff= 2 , 0
                         5081.44         1849.39
Permanent Ineff=
       F       F
Bank Sta=5012.9,5016.9
XS Rating Curve= 0 ,0
Exp/Cntr=0.3,0.1

Type RM Length L Ch R = 1 ,483     ,273,273,273
BEGIN DESCRIPTION:
Stream0307 1.0
END DESCRIPTION:
XS GIS Cut Line= 3
      1850986.67     13925013.35        1851575.       13924975.
      1851774.98     13924675.03
#Sta/Elev= 30
    4415  1936.9  4467.5 1923.13  4553.6 1895.37  4693.9 1860.43    4714 1858.43
    4734 1852.65  4928.6 1843.73  4984.7 1836.65  4992.6 1835.71  4992.8 1835.21
  4996.6 1835.71  5007.6 1836.11  5018.1 1841.95  5048.1 1843.68  5084.2 1856.82
  5105.2 1862.49  5120.3  1870.1  5146.2 1878.09  5156.3 1882.87  5162.3 1883.53
  5184.9 1891.92  5192.4 1896.89  5198.4 1897.56  5213.4 1905.36  5285.5  1929.7
  5300.5 1937.36  5321.6 1945.09  5336.6 1954.97  5357.6  1960.3  5365.1 1960.44
#Mann= 5 ,-1 , 0
    4415      .1       0  4984.7     .07       0  4992.6     .05       0
  4996.6     .07       0  5146.2      .1       0
Bank Sta=4992.6,4996.6
XS Rating Curve= 0 ,0
Exp/Cntr=0.3,0.1

Type RM Length L Ch R = 1 ,210     ,0,0,0
BEGIN DESCRIPTION:
Stream0307 0.0
END DESCRIPTION:
XS GIS Cut Line= 4
      1850957.33     13925084.41      1851454.86     13925264.18
      1851856.19     13925188.93      1852143.83     13924738.71
#Sta/Elev= 30
    4298  1948.3    4313 1939.82  4444.4 1891.22  4593.2 1842.91  4606.6 1842.05
  4918.7 1838.23  5011.9 1832.14  5012.2 1831.64  5015.9 1832.14  5040.8 1836.95
  5124.2 1837.95    5418 1835.07  5456.2 1837.32  5504.7 1845.84  5519.9 1853.83
  5541.1 1857.66  5556.3 1867.18  5577.5 1870.51  5613.8 1887.44    5635 1890.63
  5650.2 1900.01  5671.4 1903.65  5686.6 1911.53  5707.7 1913.87    5723 1922.31
  5738.2 1925.44  5744.1 1923.68  5759.3 1933.26  5765.3 1930.43  5769.6 1934.08
#Mann= 5 ,-1 , 0
    4298      .1       0  4606.6     .07       0  5011.9     .05       0
  5015.9     .07       0  5456.2      .1       0
#Block Obstruct= 2 , 0
                         5176.94          1838.2
Bank Sta=5011.9,5015.9
XS Rating Curve= 0 ,0
Exp/Cntr=0.3,0.1

Chan Stop Cuts=-1
Use User Specified Reach Order=0
Composite Channel Slope=5