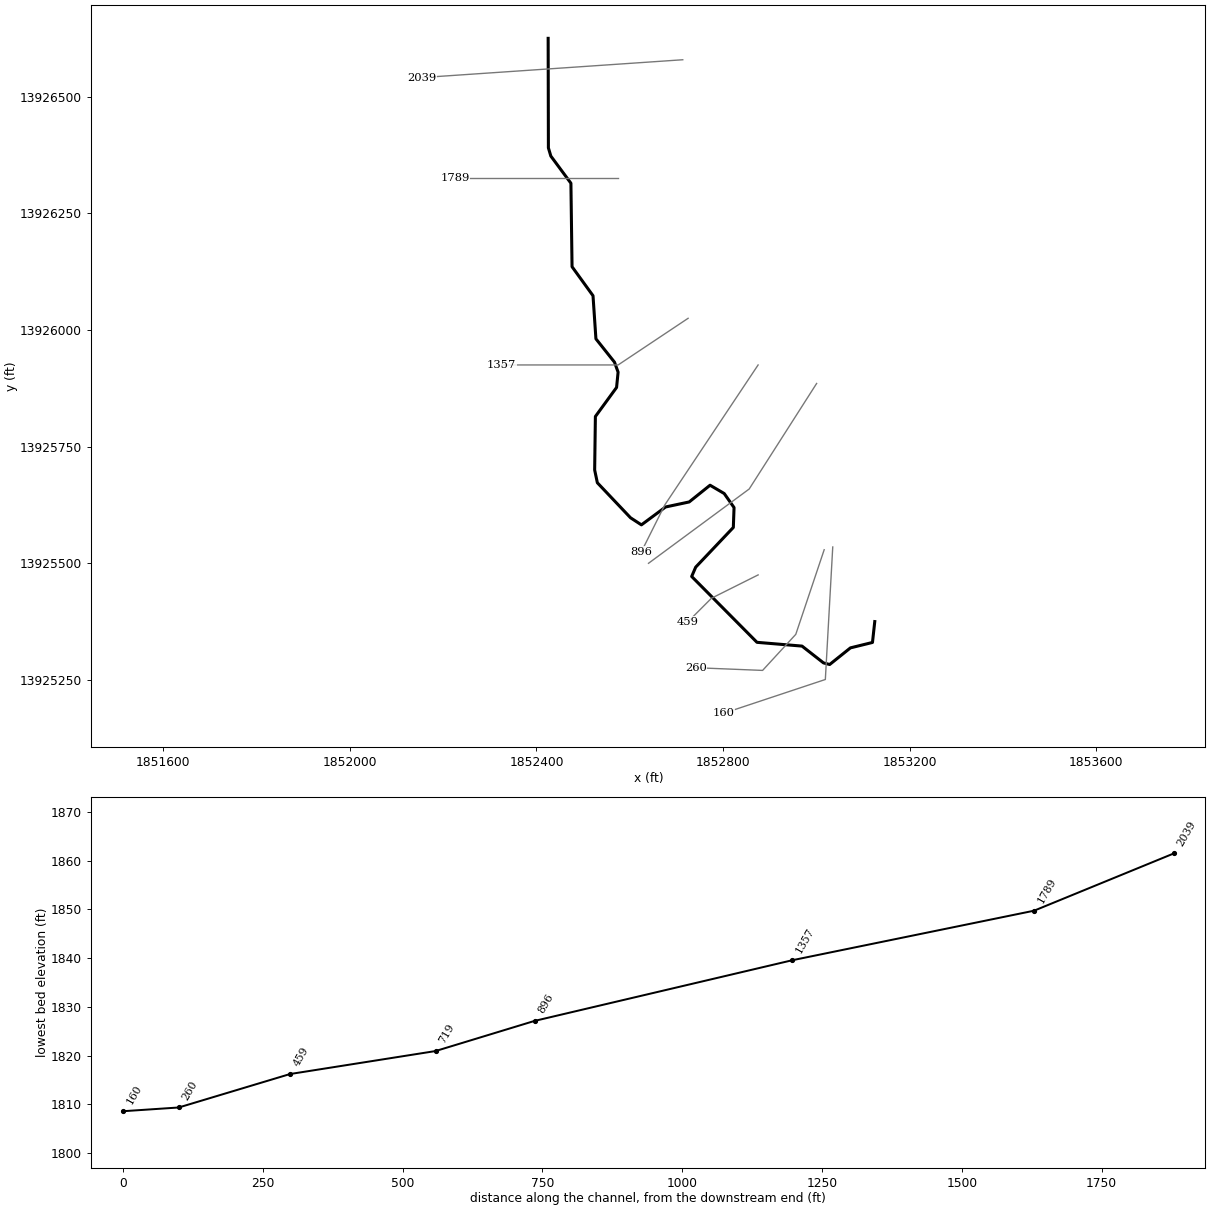
--- Stream0308.prj (project) ---

Proj Title=Stream0308 Base Level Engineering
Current Plan=p01
Default Exp/Contr=0.3,0.1
English Units
Geom File=g01
Flow File=f01
Plan File=p01
BEGIN DESCRIPTION:
Stream0308
END DESCRIPTION:

--- Stream0308.p01 (plan) ---

Plan Title=Multiple Run
Short Identifier=Multiple
Geom File=g01
Flow File=f01
Subcritical Flow
K Sum by GR= 0
Std Step Tol= 0.01
Critical Tol= 0.01
Num of Std Step Trials= 20
Max Error Tol= 0.3
Flow Tol Ratio= 0.001
Split Flow NTrial= 30
Split Flow Tol= 0.02
Split Flow Ratio= 0.02
Log Output Level= 0
Friction Slope Method= 1
Unsteady Friction Slope Method= 2
Unsteady Bridges Friction Slope Method= 1
Parabolic Critical Depth
Global Vel Dist=  1 , 1 , 1
Global Log Level= 0
CheckData=True
Encroach Param= -1, 0, 0, 0
BEGIN DESCRIPTION:
Multiple Run
END DESCRIPTION:

--- Stream0308.f01 (steady flow) ---

Flow Title=Multiple
Number of Profiles=7
Profile Names=10-year,25-year,50-year,1pct_min,100-year,1pct_plu,500-year
River Rch & RM= Stream0308,Reach-1,2039
     391     632     851     557    1111    2217    1866
Boundary for River Rch & Prof#=Stream0308,Reach-1,1
Up Type=0
Dn Type=3
Dn Slope=0.005
Boundary for River Rch & Prof#=Stream0308,Reach-1,2
Up Type=0
Dn Type=3
Dn Slope=0.005
Boundary for River Rch & Prof#=Stream0308,Reach-1,3
Up Type=0
Dn Type=3
Dn Slope=0.005
Boundary for River Rch & Prof#=Stream0308,Reach-1,4
Up Type=0
Dn Type=3
Dn Slope=0.005
Boundary for River Rch & Prof#=Stream0308,Reach-1,5
Up Type=0
Dn Type=3
Dn Slope=0.005
Boundary for River Rch & Prof#=Stream0308,Reach-1,6
Up Type=0
Dn Type=3
Dn Slope=0.005
Boundary for River Rch & Prof#=Stream0308,Reach-1,7
Up Type=0
Dn Type=3
Dn Slope=0.005

--- Stream0308.g01 (geometry) ---

Geom Title=Existing Conditions

River Reach=Stream0308,Reach-1
Reach XY= 30
      1852425.00     13926625.00      1852425.52     13926390.22
      1852430.75     13926372.67      1852473.78     13926314.49
      1852476.22     13926135.50      1852521.14     13926073.40
      1852527.38     13925980.97      1852567.19     13925930.92
      1852574.91     13925909.61      1852571.63     13925876.74
      1852526.23     13925814.50      1852524.68     13925699.88
      1852530.45     13925672.52      1852601.59     13925597.42
      1852624.90     13925582.28      1852676.65     13925620.60
      1852727.30     13925631.38      1852772.00     13925667.24
      1852802.32     13925649.42      1852823.42     13925619.35
      1852821.88     13925576.71      1852741.23     13925491.65
      1852732.60     13925471.66      1852872.57     13925330.52
      1852969.11     13925322.45      1853015.11     13925286.44
      1853028.35     13925282.98      1853072.87     13925318.64
      1853120.08     13925330.23      1853125.00     13925375.00

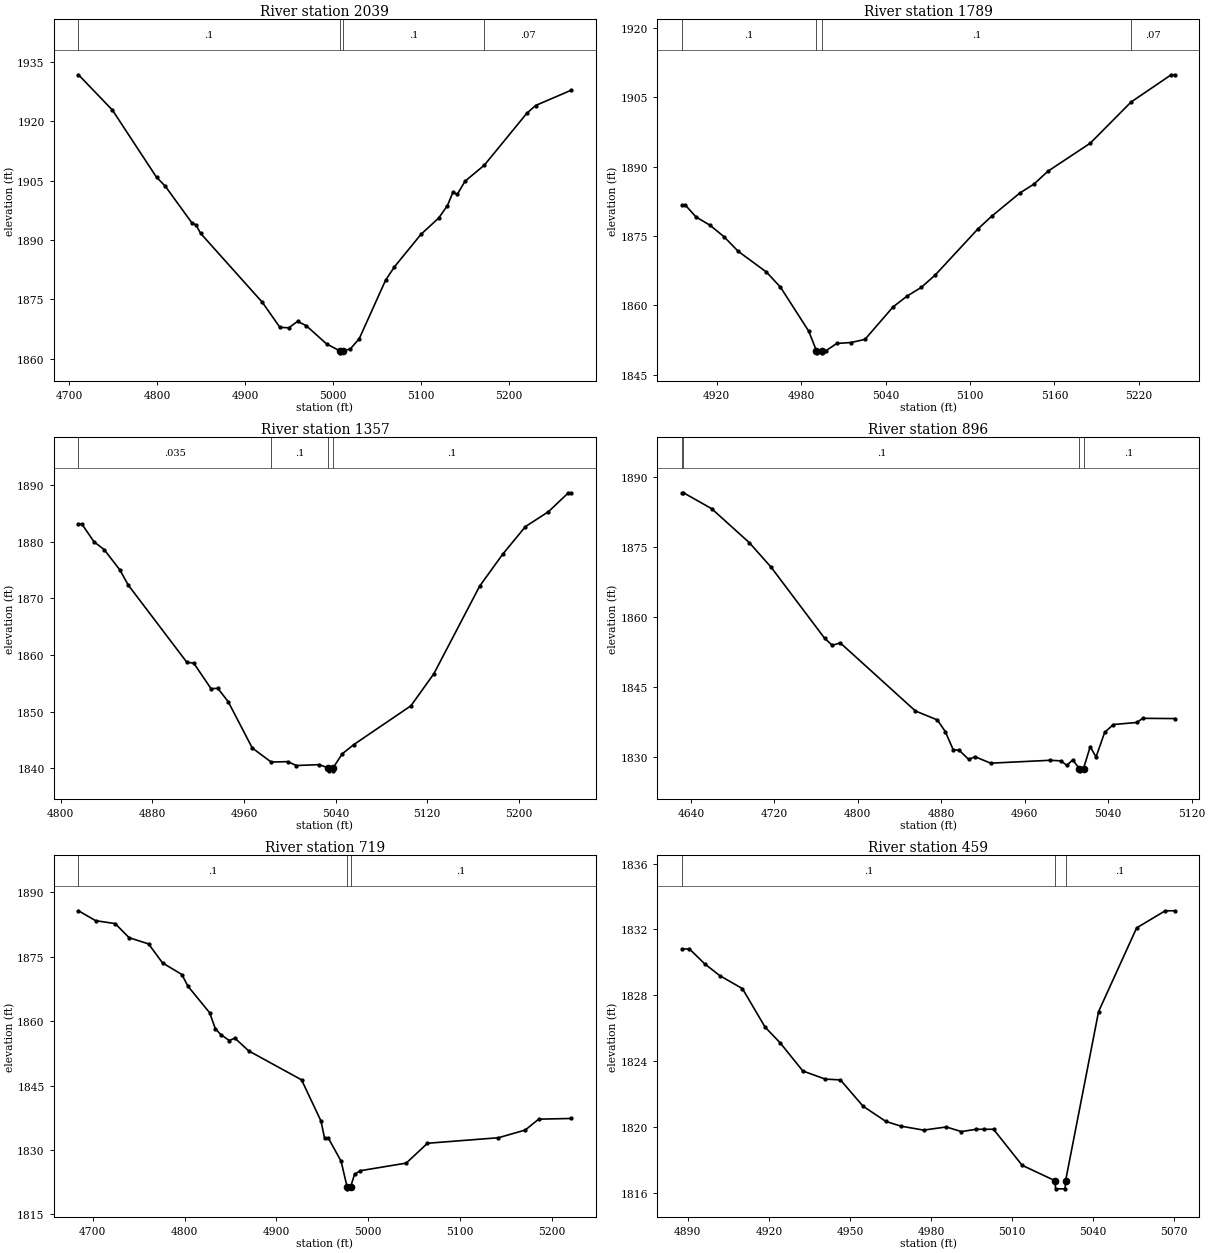
Type RM Length L Ch R = 1,2039,250,250,250
BEGIN DESCRIPTION:
Stream0308 5.0
END DESCRIPTION:
XS GIS Cut Line= 2
      1852713.50     13926579.10      1852154.51     13926540.91
#Sta/Elev= 30
  4710.8 1931.74  4749.4 1922.81  4799.5 1905.85  4809.5 1903.58  4839.5 1894.39
  4844.5 1893.75  4849.6 1891.68  4919.8 1874.25  4939.8 1867.91  4949.9 1867.80
  4959.9 1869.42  4969.9 1868.31  4993.0 1863.70  5008.0 1861.97  5008.2 1861.47
  5012.0 1861.97  5020.0 1862.49  5030.0 1865.04  5060.1 1879.89  5070.1 1883.22
  5100.2 1891.42  5120.3 1895.53  5130.3 1898.68  5136.5 1902.04  5141.5 1901.53
  5150.3 1904.84  5172.3 1908.91  5220.5 1922.00  5230.5 1923.97  5271.1 1927.85
#Mann=4,-1,0
  4710.8     0.1       0  5008.0    0.05       0  5012.0     0.1       0
  5172.3    0.07       0
Bank Sta=5008,5012
Exp/Cntr=0.3,0.1

Type RM Length L Ch R = 1,1789,432,432,432
BEGIN DESCRIPTION:
Stream0308 4.0
END DESCRIPTION:
XS GIS Cut Line= 3
      1852575.03     13926325.00      1852475.00     13926325.00
      1852225.03     13926325.00
#Sta/Elev= 30
  4895.4 1881.66  4897.9 1881.66  4905.4 1879.13  4915.4 1877.32  4925.4 1874.82
  4935.4 1871.68  4955.4 1867.21  4965.4 1863.93  4985.4 1854.44  4990.9 1850.22
  4991.2 1849.72  4994.7 1849.72  4994.9 1850.22  4997.9 1850.22  5005.4 1851.75
  5015.4 1851.95  5025.4 1852.63  5045.4 1859.67  5055.4 1862.02  5065.4 1863.88
  5075.4 1866.59  5105.4 1876.46  5115.4 1879.28  5135.4 1884.30  5145.4 1886.23
  5155.4 1889.03  5185.4 1895.08  5214.4 1903.99  5242.9 1909.89  5245.4 1909.89
#Mann=4,-1,0
  4895.4     0.1       0  4990.9    0.05       0  4994.9     0.1       0
  5214.4    0.07       0
Bank Sta=4990.9,4994.9
Exp/Cntr=0.3,0.1

Type RM Length L Ch R = 1,1357,461,461,461
BEGIN DESCRIPTION:
Stream0308 3.0
END DESCRIPTION:
XS GIS Cut Line= 3
      1852724.97     13926024.98      1852575.00     13925925.00
      1852325.04     13925925.00
#Sta/Elev= 30
  4815.5 1883.08  4818.5 1883.08  4829.0 1879.98  4838.0 1878.57  4851.5 1875.04
  4859.0 1872.32  4910.1 1858.71  4916.1 1858.57  4931.1 1854.09  4937.2 1854.10
  4946.2 1851.77  4967.2 1843.60  4983.7 1841.12  4998.2 1841.19  5005.7 1840.51
  5025.7 1840.66  5033.7 1840.07  5034.0 1839.57  5037.5 1839.57  5037.7 1840.07
  5045.7 1842.56  5055.7 1844.18  5105.7 1851.04  5125.7 1856.68  5165.7 1872.14
  5185.7 1877.74  5205.7 1882.65  5225.7 1885.26  5243.2 1888.61  5245.7 1888.61
#Mann=4,-1,0
  4815.5   0.035       0  4983.7     0.1       0  5033.7    0.05       0
  5037.7     0.1       0
Bank Sta=5033.7,5037.7
Exp/Cntr=0.3,0.1

Type RM Length L Ch R = 1,896,177,177,177
BEGIN DESCRIPTION:
Stream0308 2.0
END DESCRIPTION:
XS GIS Cut Line= 3
      1852874.98     13925924.97      1852675.00     13925625.00
      1852625.01     13925525.02
#Sta/Elev= 30
  4631.4 1886.59  4632.9 1886.59  4659.9 1883.19  4696.0 1875.92  4717.0 1870.64
  4768.1 1855.49  4775.6 1853.95  4783.1 1854.50  4855.2 1839.92  4876.2 1838.01
  4883.8 1835.53  4891.3 1831.68  4897.3 1831.48  4906.3 1829.55  4912.3 1830.14
  4927.3 1828.76  4984.4 1829.38  4994.7 1829.25  5000.3 1828.29  5005.9 1829.46
  5012.3 1827.62  5012.5 1827.12  5016.3 1827.62  5022.7 1832.29  5028.3 1830.08
  5036.6 1835.37  5045.0 1837.03  5067.4 1837.46  5073.0 1838.35  5103.7 1838.30
#Mann=4,-1,0
  4631.4   0.035       0  4632.9     0.1       0  5012.3    0.05       0
  5016.3     0.1       0
Bank Sta=5012.3,5016.3
Exp/Cntr=0.3,0.1

Type RM Length L Ch R = 1,719,260,260,260
BEGIN DESCRIPTION:
Mapping XS 3343d8ab
END DESCRIPTION:
XS GIS Cut Line= 3
      1853000.39     13925885.32      1852855.88     13925659.15
      1852640.09     13925499.89
#Sta/Elev= 30
  4684.4 1885.74  4703.1 1883.43  4724.3 1882.76  4739.5 1879.47  4760.7 1878.02
  4775.9 1873.60  4797.0 1870.88  4803.5 1868.18  4827.2 1861.98  4833.4 1858.26
  4839.3 1856.90  4848.6 1855.50  4854.6 1856.07  4869.8 1853.08  4927.3 1846.34
  4948.5 1836.72  4952.3 1832.76  4956.5 1832.76  4970.4 1827.35  4976.8 1821.44
  4977.0 1820.94  4980.8 1821.44  4985.0 1824.33  4991.2 1825.16  5041.3 1826.94
  5064.4 1831.56  5141.6 1832.85  5170.8 1834.63  5185.5 1837.18  5221.0 1837.34
#Mann=3,-1,0
  4684.4     0.1       0  4976.8    0.05       0  4980.8     0.1       0
Bank Sta=4976.8,4980.8
Exp/Cntr=0.3,0.1

Type RM Length L Ch R = 1,459,199,199,199
BEGIN DESCRIPTION:
Stream0308 1.0
END DESCRIPTION:
XS GIS Cut Line= 3
      1852875.03     13925475.02      1852775.00     13925425.00
      1852725.04     13925375.04
#Sta/Elev= 28
  4887.8 1830.81  4890.6 1830.81  4896.2 1829.91  4901.8 1829.19  4910.2 1828.40
  4918.6 1826.06  4924.2 1825.10  4932.6 1823.39  4940.9 1822.90  4946.5 1822.85
  4954.9 1821.25  4963.3 1820.33  4968.9 1820.04  4977.3 1819.80  4985.7 1819.99
  4991.3 1819.71  4996.8 1819.85  4999.6 1819.85  5003.2 1819.85  5013.8 1817.66
  5025.9 1816.73  5026.2 1816.23  5029.7 1816.23  5029.9 1816.73  5042.1 1827.00
  5056.2 1832.09  5066.8 1833.13  5070.3 1833.13
#Mann=3,-1,0
  4887.8     0.1       0  5025.9    0.05       0  5029.9     0.1       0
Bank Sta=5025.9,5029.9
Exp/Cntr=0.3,0.1

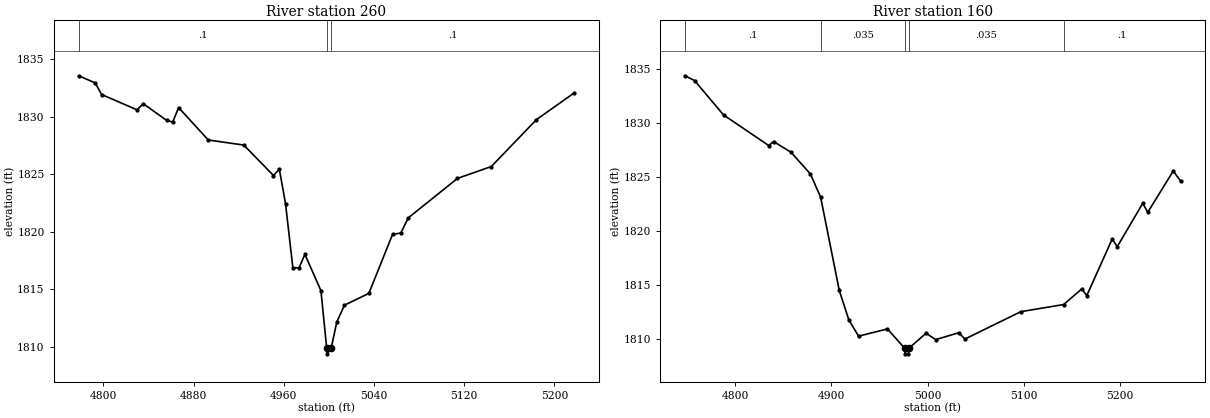
Type RM Length L Ch R = 1,260,100,100,100
BEGIN DESCRIPTION:
Stream0306 0.1
END DESCRIPTION:
XS GIS Cut Line= 4
      1853016.59     13925528.96      1852955.73     13925347.63
      1852884.60     13925270.33      1852741.54     13925276.10
#Sta/Elev= 30
  4778.0 1833.57  4792.7 1832.95  4798.4 1831.94  4829.9 1830.60  4835.2 1831.15
  4856.0 1829.69  4861.4 1829.54  4866.7 1830.80  4893.0 1827.98  4924.5 1827.54
  4950.8 1824.89  4956.0 1825.44  4961.5 1822.44  4968.0 1816.86  4973.5 1816.86
  4978.7 1818.02  4992.9 1814.87  4998.0 1809.87  4998.3 1809.37  5002.0 1809.87
  5007.0 1812.15  5013.8 1813.61  5035.4 1814.63  5056.4 1819.76  5063.8 1819.89
  5070.3 1821.20  5114.0 1824.64  5144.0 1825.67  5184.0 1829.75  5217.5 1832.08
#Mann=3,-1,0
  4778.0     0.1       0  4998.0    0.05       0  5002.0     0.1       0
Bank Sta=4998,5002
Exp/Cntr=0.3,0.1

Type RM Length L Ch R = 1,160,0,0,0
BEGIN DESCRIPTION:
Stream0308 0.2
END DESCRIPTION:
XS GIS Cut Line= 3
      1853034.96     13925534.88      1853019.07     13925250.87
      1852800.57     13925178.25
#Sta/Elev= 30
  4748.1 1834.38  4758.0 1833.93  4788.0 1830.75  4835.0 1827.91  4840.0 1828.28
  4858.1 1827.29  4878.2 1825.28  4888.9 1823.12  4908.2 1814.49  4918.2 1811.74
  4928.3 1810.24  4958.3 1810.91  4976.3 1809.10  4976.6 1808.60  4980.1 1808.60
  4980.3 1809.10  4998.4 1810.51  5008.4 1809.92  5032.5 1810.56  5038.7 1809.97
  5096.8 1812.51  5141.3 1813.17  5160.1 1814.62  5165.3 1814.00  5191.7 1819.24
  5197.0 1818.54  5223.4 1822.55  5228.7 1821.73  5255.1 1825.55  5262.8 1824.62
#Mann=5,-1,0
  4748.1     0.1       0  4888.9   0.035       0  4976.3   0.035       0
  4980.3   0.035       0  5141.3     0.1       0
Bank Sta=4976.3,4980.3
Exp/Cntr=0.3,0.1

Chan Stop Cuts=-1