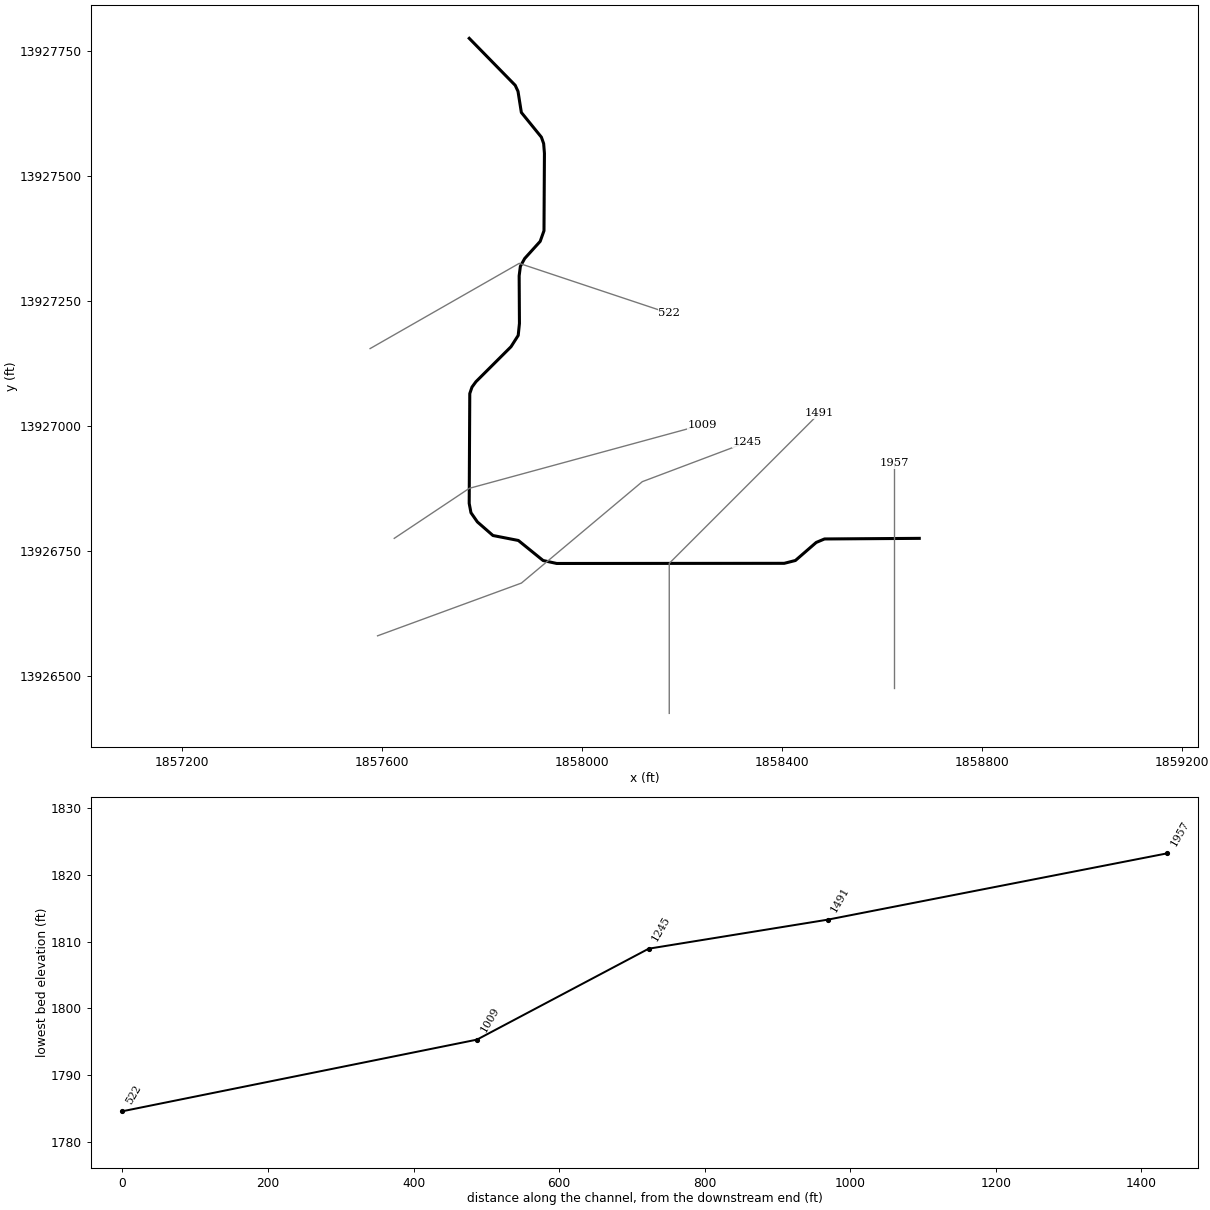
--- Stream0309.prj (project) ---

Proj Title=Stream0309 Base Level Engineering
Current Plan=p01
Default Exp/Contr=0.3,0.1
English Units
Geom File=g01
Flow File=f01
Plan File=p01
Y Axis Title=Elevation
X Axis Title(PF)=Main Channel Distance
X Axis Title(XS)=Station
BEGIN DESCRIPTION:
Stream0309
END DESCRIPTION:
DSS Export Rating Curves= 0
DSS Export Rating Curve Sorted= 0
DSS Export Volume Flow Curves= 0
DXF OffsetX= 0
DXF OffsetY= 0
DXF ScaleX= 1
DXF ScaleY= 10

--- Stream0309.p01 (plan) ---

Plan Title=Multiple Run
Short Identifier=Multiple
Geom File=g01
Flow File=f01
Subcritical Flow
K Sum by GR= 0
Std Step Tol= 0.01
Critical Tol= 0.01
Num of Std Step Trials= 20
Max Error Tol= 0.3
Flow Tol Ratio= 0.001
Split Flow NTrial= 30
Split Flow Tol= 0.02
Split Flow Ratio= 0.02
Log Output Level= 0
Friction Slope Method= 1
Unsteady Friction Slope Method= 2
Unsteady Bridges Friction Slope Method= 1
Parabolic Critical Depth
Global Vel Dist=  1 , 1 , 1
Global Log Level= 0
CheckData=True
Encroach Param= -1, 0, 0, 0
BEGIN DESCRIPTION:
Multiple Run
END DESCRIPTION:

--- Stream0309.f01 (steady flow) ---

Flow Title=Multiple
Number of Profiles=7
Profile Names=10-year,25-year,50-year,1pct_min,100-year,1pct_plu,500-year
River Rch & RM= Stream0309,Reach-1,1957
     705    1183    1632    1092    2179    4349    3832
Boundary for River Rch & Prof#=Stream0309,Reach-1,1
Up Type=0
Dn Type=3
Dn Slope=0.005
Boundary for River Rch & Prof#=Stream0309,Reach-1,2
Up Type=0
Dn Type=3
Dn Slope=0.005
Boundary for River Rch & Prof#=Stream0309,Reach-1,3
Up Type=0
Dn Type=3
Dn Slope=0.005
Boundary for River Rch & Prof#=Stream0309,Reach-1,4
Up Type=0
Dn Type=3
Dn Slope=0.005
Boundary for River Rch & Prof#=Stream0309,Reach-1,5
Up Type=0
Dn Type=3
Dn Slope=0.005
Boundary for River Rch & Prof#=Stream0309,Reach-1,6
Up Type=0
Dn Type=3
Dn Slope=0.005
Boundary for River Rch & Prof#=Stream0309,Reach-1,7
Up Type=0
Dn Type=3
Dn Slope=0.005

--- Stream0309.g01 (geometry) ---

Geom Title=Existing Conditions
Program Version=4.10

River Reach=Stream0309      ,Reach-1
Reach XY= 30
        1858675.       13926775.       1858485.5     13926773.79
      1858468.94     13926766.86      1858427.33     13926730.75
      1858404.97     13926725.07      1857949.91     13926724.79
      1857922.65     13926730.71      1857873.22     13926770.77
      1857822.41     13926780.71      1857791.27     13926807.86
      1857778.45     13926826.25      1857774.91     13926844.88
      1857776.06     13927064.56      1857780.48     13927077.45
       1857788.4     13927088.31      1857858.53     13927158.25
      1857872.92     13927180.86       1857875.4     13927204.84
      1857874.82     13927300.07      1857877.27     13927319.06
      1857885.86     13927334.64      1857916.86     13927368.94
      1857924.48     13927390.22      1857925.37     13927545.15
       1857923.8      13927564.5      1857919.29     13927577.35
      1857879.21     13927626.74      1857872.52     13927668.97
      1857866.91     13927681.08        1857775.       13927775.

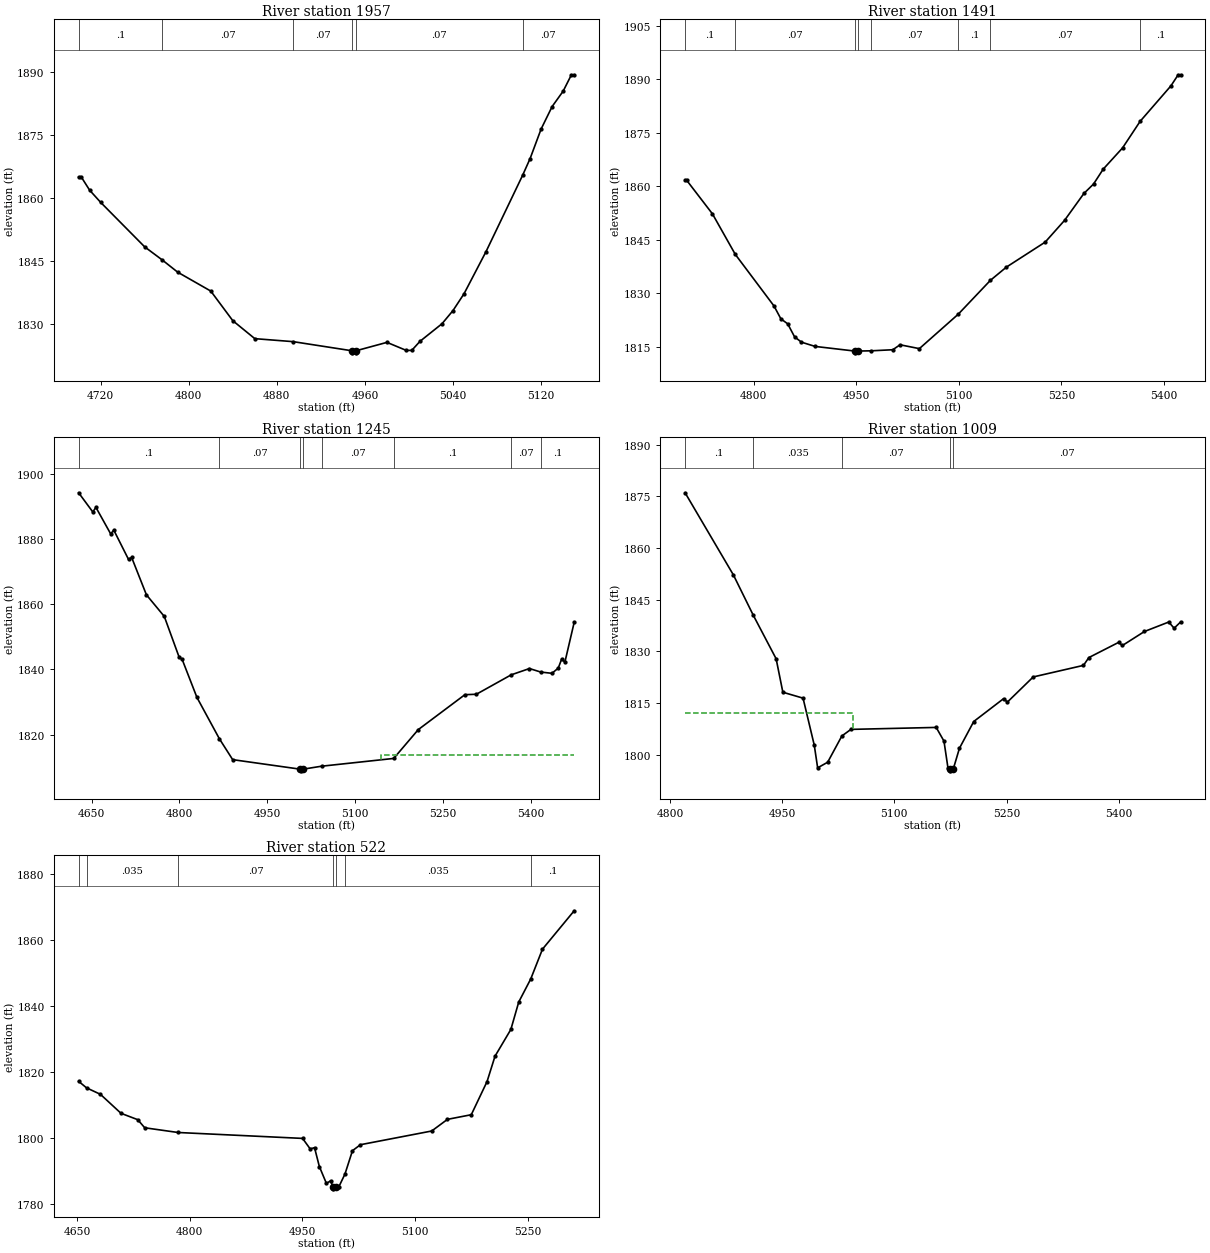
Type RM Length L Ch R = 1 ,1957    ,466,466,466
BEGIN DESCRIPTION:
Stream0309 4.0
END DESCRIPTION:
XS GIS Cut Line= 3
        1858625.     13926475.04        1858625.       13926775.
        1858625.     13926925.04
#Sta/Elev= 30
    4700 1864.96  4702.5 1864.96    4710 1861.86    4720 1858.97    4760 1848.39
  4775.8 1845.31    4790 1842.37    4820 1837.89    4840 1830.85    4860 1826.58
  4894.8 1825.87    4948 1823.71  4948.2 1823.21  4951.7 1823.21    4952 1823.71
    4980  1825.7  4997.5 1823.79  5002.5 1823.79    5010 1825.95    5030 1830.13
    5040 1833.27    5050 1837.26    5070 1847.29  5103.2 1865.41    5110 1869.39
    5120 1876.41    5130 1881.75    5140  1885.4  5147.5 1889.29    5150 1889.29
#Mann= 6 ,-1 , 0
    4700      .1       0  4775.8     .07       0  4894.8     .07       0
    4948     .05       0    4952     .07       0  5103.2     .07       0
Bank Sta=4948,4952
XS Rating Curve= 0 ,0
Exp/Cntr=0.3,0.1

Type RM Length L Ch R = 1 ,1491    ,246,246,246
BEGIN DESCRIPTION:
Stream0309 3.0
END DESCRIPTION:
XS GIS Cut Line= 3
        1858175.     13926424.98        1858175.       13926725.
      1858475.01     13927025.01
#Sta/Elev= 30
    4700 1861.64  4702.5 1861.64    4740 1852.26  4773.4 1840.89    4830 1826.41
    4840 1822.82    4850 1821.41    4860 1817.77    4870 1816.28    4890 1815.08
    4948 1813.78  4948.3 1813.28    4952 1813.78  4972.2 1813.85  5003.6 1814.15
  5014.2 1815.54  5042.4 1814.46  5099.2 1824.11  5146.3 1833.63  5169.7 1837.34
  5226.3 1844.34  5254.6 1850.44  5282.9 1857.99    5297 1860.64  5311.1 1864.81
  5339.4 1870.77  5365.1 1878.23  5410.1 1888.18  5420.7 1891.29  5424.3 1891.29
#Mann= 8 ,-1 , 0
    4700      .1       0  4773.4     .07       0    4948     .05       0
    4952     .07       0  4972.2     .07       0  5099.2      .1       0
  5146.3     .07       0  5365.1      .1       0
Bank Sta=4948,4952
XS Rating Curve= 0 ,0
Exp/Cntr=0.3,0.1

Type RM Length L Ch R = 1 ,1245    ,236,236,236
BEGIN DESCRIPTION:
Stream0309 2.1
END DESCRIPTION:
XS GIS Cut Line= 4
      1857591.65     13926580.08      1857879.39     13926685.59
      1858121.11     13926888.38      1858330.43     13926967.29
#Sta/Elev= 30
    4628 1894.15  4652.2 1888.27  4657.5 1889.68  4682.7 1881.55    4688 1882.71
  4713.2 1873.71  4718.5 1874.32  4743.7 1862.87  4774.2 1856.25  4799.4 1843.83
  4804.7 1843.07  4829.9 1831.43  4868.3 1818.73  4890.9 1812.36  5006.6 1809.43
  5006.8 1808.93  5010.6 1809.43  5042.6 1810.35  5165.7 1812.73  5207.6 1821.56
  5287.2 1832.27  5306.8  1832.4  5366.2 1838.35  5397.4 1840.28  5416.8  1839.2
  5435.8 1838.82  5446.5 1840.41  5452.5 1843.25  5457.8  1842.2  5473.7 1854.43
#Mann= 8 ,-1 , 0
    4628      .1       0  4868.3     .07       0  5006.6     .05       0
  5010.6     .07       0  5042.6     .07       0  5165.7      .1       0
  5366.2     .07       0  5416.8      .1       0
#XS Ineff= 2 , 0
                         5143.23         1813.68
Permanent Ineff=
       F       F
Bank Sta=5006.6,5010.6
XS Rating Curve= 0 ,0
Exp/Cntr=0.3,0.1

Type RM Length L Ch R = 1 ,1009    ,487,487,487
BEGIN DESCRIPTION:
Stream0309 2.0
END DESCRIPTION:
XS GIS Cut Line= 3
      1857625.03     13926775.02        1857775.       13926875.
       1858240.3     13927001.74
#Sta/Elev= 30
  4820.3 1876.06  4884.9 1852.19  4911.4 1840.51    4942 1827.85    4951 1818.13
    4978 1816.41    4993 1802.75  4997.5 1796.17  5010.9  1797.8  5029.9 1805.43
    5042 1807.34    5156 1807.91  5166.4 1803.93  5171.7  1796.2  5174.8  1795.8
  5175.1  1795.3  5178.8  1795.8  5187.1 1801.87  5206.2 1809.63    5246 1816.25
  5251.2 1815.27  5285.7 1822.57  5352.9 1825.93  5360.1  1828.2  5399.8  1832.6
    5405 1831.71  5434.4 1835.77  5466.9 1838.52  5474.1 1836.72  5482.8 1838.55
#Mann= 5 ,-1 , 0
  4820.3      .1       0  4911.4    .035       0  5029.9     .07       0
  5174.8     .05       0  5178.8     .07       0
#XS Ineff= 2 , 0
         5044.77 1812.08
Permanent Ineff=
       F       F
Bank Sta=5174.8,5178.8
XS Rating Curve= 0 ,0
Exp/Cntr=0.3,0.1

Type RM Length L Ch R = 1 ,522     ,0,0,0
BEGIN DESCRIPTION:
Stream0309 1.0
END DESCRIPTION:
XS GIS Cut Line= 3
      1857576.71     13927154.52        1857875.       13927325.
      1858175.01       13927225.
#Sta/Elev= 30
  4652.3 1817.13  4662.8 1815.15  4681.3 1813.19  4708.7 1807.44    4731 1805.51
  4740.3 1803.06  4784.7 1801.63  4950.5 1799.84  4960.6 1796.66  4966.4 1797.04
  4972.8 1791.33  4982.2 1786.22  4987.9 1787.01    4991 1785.07  4991.2 1784.57
    4995 1785.07  4998.5 1785.07  5006.9 1789.04  5016.9 1796.12  5027.5 1797.93
  5122.4 1802.08  5143.4 1805.61  5175.1 1807.01  5196.1 1817.05  5206.7 1824.73
  5227.8 1832.83  5238.3 1841.14  5254.3 1848.13  5269.9 1857.14  5312.1 1868.76
#Mann= 7 ,-1 , 0
  4652.3    .063       0  4662.8    .035       0  4784.7     .07       0
    4991     .05       0    4995     .07       0  5006.9    .035       0
  5254.3      .1       0
Bank Sta=4991,4995
XS Rating Curve= 0 ,0
Exp/Cntr=0.3,0.1

Chan Stop Cuts=-1
Use User Specified Reach Order=0
Composite Channel Slope=5