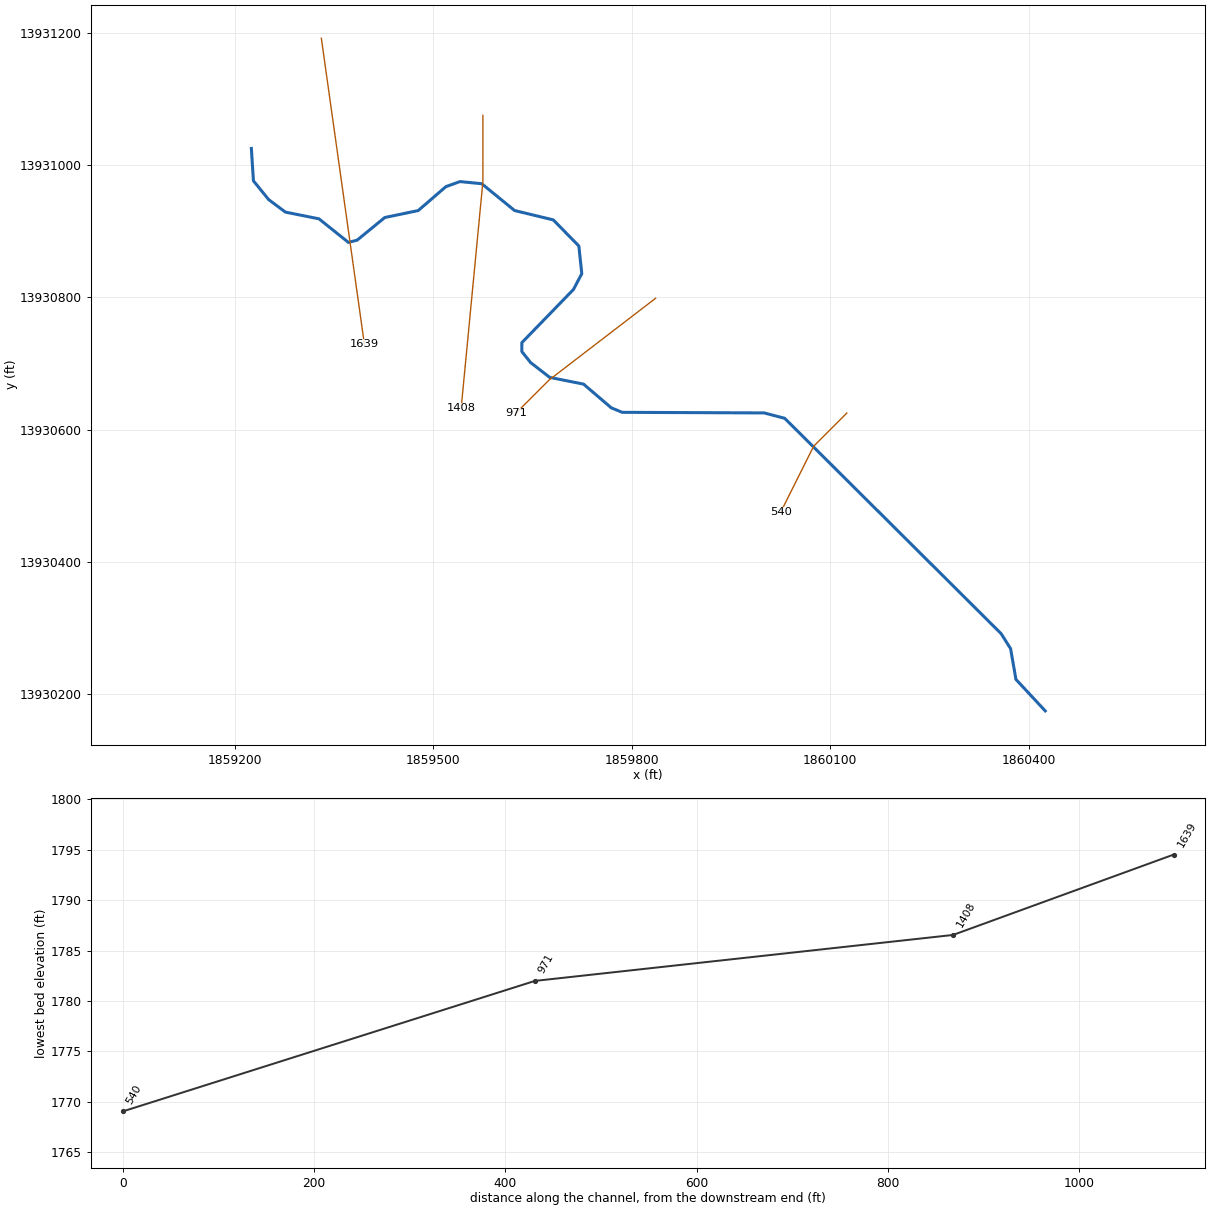
--- Stream0310.prj (project) ---

Proj Title=Stream0310 Base Level Engineering
Current Plan=p01
Default Exp/Contr=0.3,0.1
English Units
Geom File=g01
Flow File=f01
Plan File=p01
BEGIN DESCRIPTION:
Stream0310
END DESCRIPTION:

--- Stream0310.p01 (plan) ---

Plan Title=Multiple Run
Short Identifier=Multiple
Geom File=g01
Flow File=f01
Subcritical Flow
K Sum by GR= 0
Std Step Tol= 0.01
Critical Tol= 0.01
Num of Std Step Trials= 20
Max Error Tol= 0.3
Flow Tol Ratio= 0.001
Split Flow NTrial= 30
Split Flow Tol= 0.02
Split Flow Ratio= 0.02
Log Output Level= 0
Friction Slope Method= 1
Unsteady Friction Slope Method= 2
Unsteady Bridges Friction Slope Method= 1
Parabolic Critical Depth
Global Vel Dist=  1 , 1 , 1
Global Log Level= 0
CheckData=True
Encroach Param= -1, 0, 0, 0
BEGIN DESCRIPTION:
Multiple Run
END DESCRIPTION:

--- Stream0310.f01 (steady flow) ---

Flow Title=Multiple
Number of Profiles=7
Profile Names=10-year,25-year,50-year,1pct_min,100-year,1pct_plu,500-year
River Rch & RM= Stream0310,Reach-1,1639
     756    1277    1769    1187    2369    4727    4195
Boundary for River Rch & Prof#=Stream0310,Reach-1,1
Up Type=0
Dn Type=3
Dn Slope=0.005
Boundary for River Rch & Prof#=Stream0310,Reach-1,2
Up Type=0
Dn Type=3
Dn Slope=0.005
Boundary for River Rch & Prof#=Stream0310,Reach-1,3
Up Type=0
Dn Type=3
Dn Slope=0.005
Boundary for River Rch & Prof#=Stream0310,Reach-1,4
Up Type=0
Dn Type=3
Dn Slope=0.005
Boundary for River Rch & Prof#=Stream0310,Reach-1,5
Up Type=0
Dn Type=3
Dn Slope=0.005
Boundary for River Rch & Prof#=Stream0310,Reach-1,6
Up Type=0
Dn Type=3
Dn Slope=0.005
Boundary for River Rch & Prof#=Stream0310,Reach-1,7
Up Type=0
Dn Type=3
Dn Slope=0.005

--- Stream0310.g01 (geometry) ---

Geom Title=Existing Conditions

River Reach=Stream0310,Reach-1
Reach XY= 30
      1859225.00     13931025.00      1859228.14     13930976.03
      1859251.15     13930947.71      1859276.46     13930928.79
      1859327.27     13930918.59      1859371.69     13930883.01
      1859384.92     13930886.40      1859426.64     13930920.58
      1859477.19     13930931.13      1859519.06     13930967.23
      1859540.39     13930974.93      1859573.28     13930971.66
      1859622.84     13930931.19      1859681.44     13930916.98
      1859720.04     13930877.54      1859724.46     13930835.69
      1859711.84     13930811.80      1859633.91     13930731.50
      1859633.84     13930718.05      1859647.23     13930701.29
      1859676.14     13930678.94      1859727.12     13930668.86
      1859768.92     13930633.09      1859785.50     13930626.20
      1860000.12     13930625.30      1860031.19     13930617.19
      1860358.39     13930291.69      1860372.66     13930269.03
      1860380.71     13930222.65      1860425.00     13930175.00

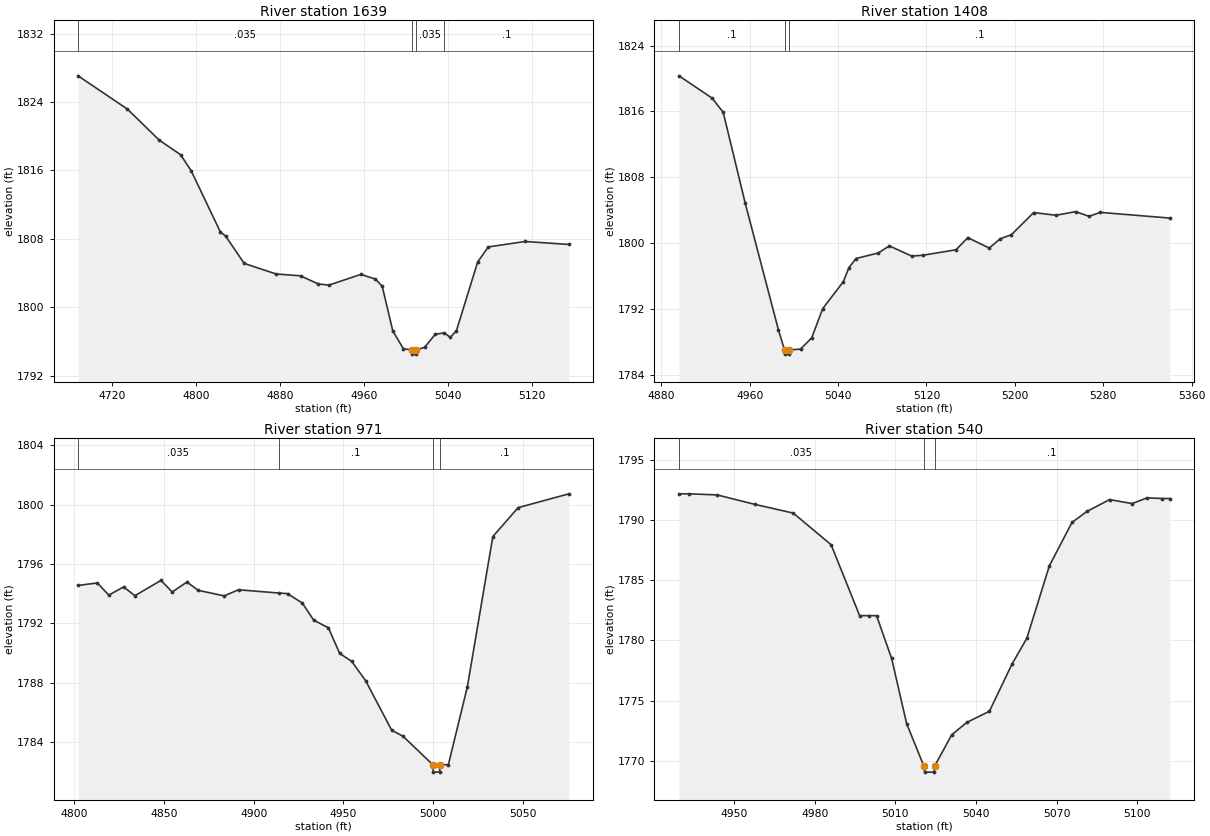
Type RM Length L Ch R = 1,1639,231,231,231
BEGIN DESCRIPTION:
Stream0310 4.0
END DESCRIPTION:
XS GIS Cut Line= 2
      1859330.78     13931191.57      1859395.86     13930729.03
#Sta/Elev= 30
  4688.0 1827.07  4735.0 1823.17  4765.3 1819.54  4785.5 1817.85  4795.6 1815.97
  4823.4 1808.81  4828.5 1808.31  4846.1 1805.12  4876.4 1803.89  4899.7 1803.67
  4916.8 1802.71  4926.9 1802.59  4957.2 1803.84  4970.9 1803.29  4977.4 1802.47
  4987.5 1797.24  4997.6 1795.13  5005.7 1795.01  5005.9 1794.51  5009.4 1794.51
  5009.7 1795.01  5017.8 1795.30  5027.9 1796.83  5036.6 1797.00  5042.2 1796.47
  5048.1 1797.25  5068.3 1805.29  5078.4 1807.05  5113.4 1807.69  5155.1 1807.34
#Mann=4,-1,0
  4688.0   0.035       0  5005.7   0.035       0  5009.7   0.035       0
  5036.6     0.1       0
Bank Sta=5005.7,5009.7
Exp/Cntr=0.3,0.1

Type RM Length L Ch R = 1,1408,437,437,437
BEGIN DESCRIPTION:
Stream0310 3.0
END DESCRIPTION:
XS GIS Cut Line= 3
      1859575.00     13931074.96      1859575.00     13930975.00
      1859542.13     13930632.34
#Sta/Elev= 30
  4896.0 1820.33  4926.0 1817.62  4936.0 1815.90  4956.0 1804.83  4986.0 1789.48
  4991.5 1787.04  4991.7 1786.54  4995.2 1786.54  4995.5 1787.04  5006.0 1787.15
  5016.1 1788.52  5026.1 1792.07  5044.7 1795.33  5049.8 1797.04  5056.2 1798.15
  5076.3 1798.82  5086.4 1799.68  5106.5 1798.45  5116.5 1798.54  5146.7 1799.21
  5157.4 1800.68  5176.8 1799.42  5186.8 1800.55  5196.9 1801.04  5217.0 1803.73
  5237.1 1803.40  5254.9 1803.84  5267.2 1803.27  5277.2 1803.75  5340.2 1803.06
#Mann=3,-1,0
  4896.0     0.1       0  4991.5    0.05       0  4995.5     0.1       0
Bank Sta=4991.5,4995.5
Exp/Cntr=0.3,0.1

Type RM Length L Ch R = 1,971,431,431,431
BEGIN DESCRIPTION:
Stream0310 2.0
END DESCRIPTION:
XS GIS Cut Line= 3
      1859836.05     13930798.56      1859675.00     13930675.00
      1859625.00     13930625.00
#Sta/Elev= 30
  4802.0 1794.56  4812.8 1794.73  4819.1 1793.91  4827.4 1794.46  4833.7 1793.87
  4848.2 1794.90  4854.5 1794.12  4862.7 1794.79  4869.0 1794.23  4883.5 1793.86
  4891.5 1794.27  4913.9 1794.05  4918.8 1794.01  4927.1 1793.37  4933.4 1792.22
  4941.6 1791.71  4947.9 1789.98  4954.6 1789.45  4962.4 1788.14  4976.9 1784.81
  4983.2 1784.41  4999.8 1782.49  5000.1 1781.99  5003.6 1781.99  5003.8 1782.49
  5008.5 1782.49  5019.1 1787.74  5033.3 1797.85  5047.4 1799.80  5075.7 1800.73
#Mann=4,-1,0
  4802.0   0.035       0  4913.9     0.1       0  4999.8    0.05       0
  5003.8     0.1       0
Bank Sta=4999.8,5003.8
Exp/Cntr=0.3,0.1

Type RM Length L Ch R = 1,540,0,0,0
BEGIN DESCRIPTION:
Stream0310 1.0
END DESCRIPTION:
XS GIS Cut Line= 3
      1860125.03     13930625.03      1860075.00     13930575.00
      1860024.98     13930474.96
#Sta/Elev= 28
  4929.5 1792.18  4933.1 1792.18  4943.7 1792.09  4957.8 1791.30  4972.0 1790.58
  4986.1 1787.95  4996.7 1782.06  5000.3 1782.06  5003.0 1782.06  5008.6 1778.51
  5014.2 1773.09  5020.6 1769.56  5020.9 1769.06  5024.4 1769.06  5024.6 1769.56
  5031.0 1772.17  5036.6 1773.19  5045.0 1774.12  5053.4 1778.04  5058.9 1780.17
  5067.3 1786.20  5075.7 1789.80  5081.3 1790.72  5089.7 1791.70  5098.1 1791.37
  5103.7 1791.85  5109.3 1791.79  5112.1 1791.79
#Mann=3,-1,0
  4929.5   0.035       0  5020.6   0.035       0  5024.6     0.1       0
Bank Sta=5020.6,5024.6
Exp/Cntr=0.3,0.1

Chan Stop Cuts=-1