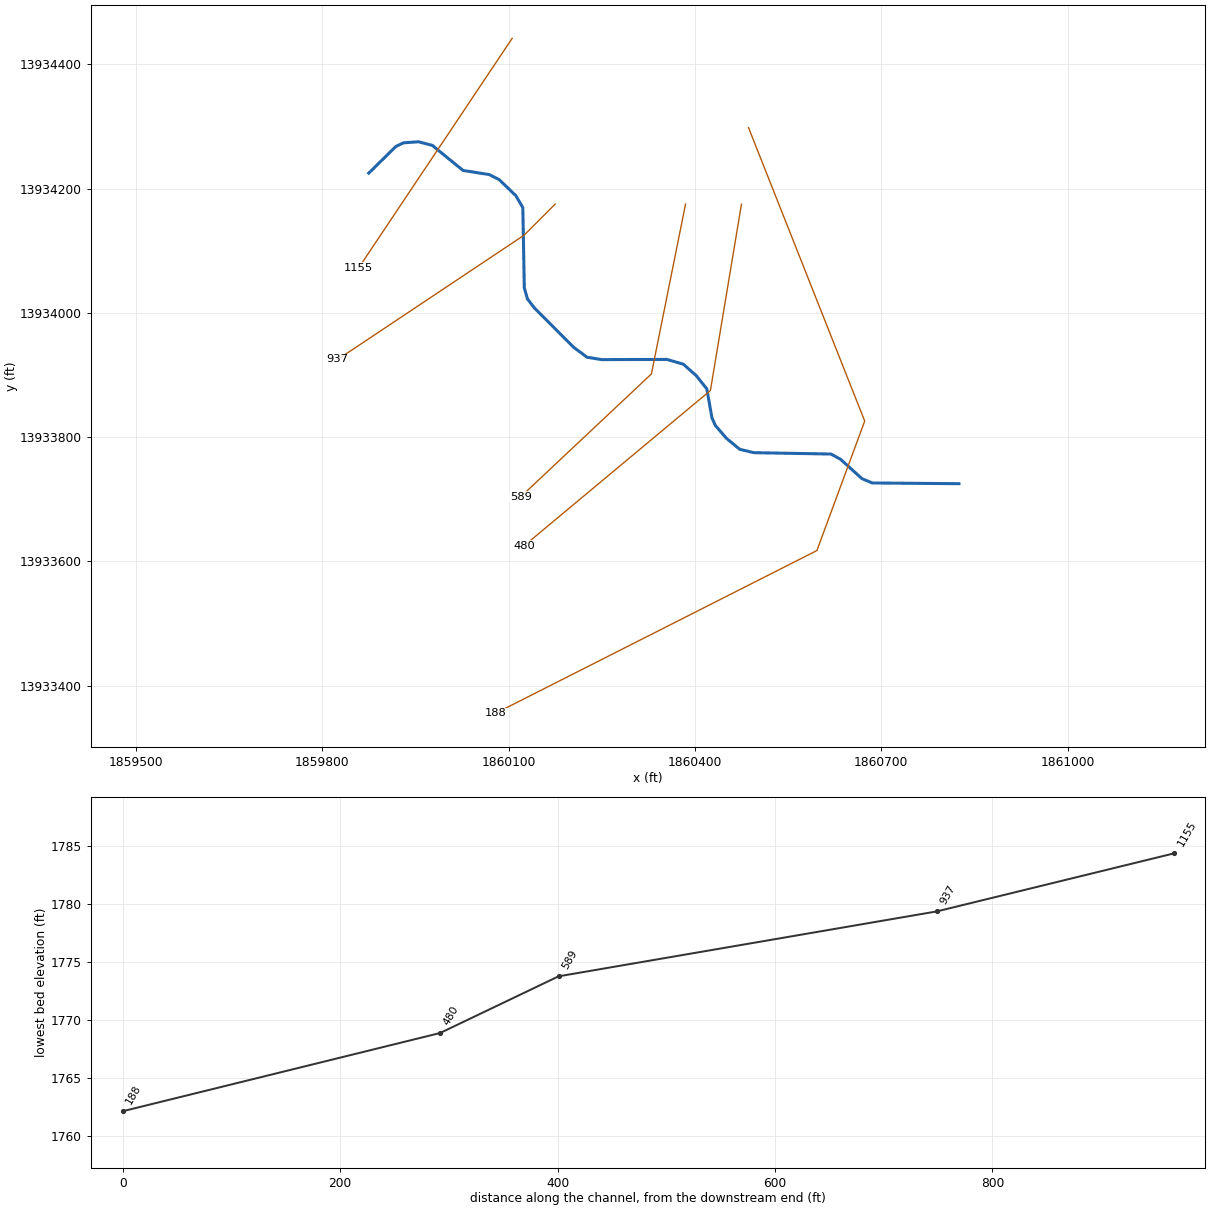
--- Stream0311.prj (project) ---

Proj Title=Stream0311 Base Level Engineering
Current Plan=p01
Default Exp/Contr=0.3,0.1
English Units
Geom File=g01
Flow File=f01
Plan File=p01
BEGIN DESCRIPTION:
Stream0311
END DESCRIPTION:

--- Stream0311.p01 (plan) ---

Plan Title=Multiple Run
Short Identifier=Multiple
Geom File=g01
Flow File=f01
Subcritical Flow
K Sum by GR= 0
Std Step Tol= 0.01
Critical Tol= 0.01
Num of Std Step Trials= 20
Max Error Tol= 0.3
Flow Tol Ratio= 0.001
Split Flow NTrial= 30
Split Flow Tol= 0.02
Split Flow Ratio= 0.02
Log Output Level= 0
Friction Slope Method= 1
Unsteady Friction Slope Method= 2
Unsteady Bridges Friction Slope Method= 1
Parabolic Critical Depth
Global Vel Dist=  1 , 1 , 1
Global Log Level= 0
CheckData=True
Encroach Param= -1, 0, 0, 0
BEGIN DESCRIPTION:
Multiple Run
END DESCRIPTION:

--- Stream0311.f01 (steady flow) ---

Flow Title=Multiple
Number of Profiles=7
Profile Names=10-year,25-year,50-year,1pct_min,100-year,1pct_plu,500-year
River Rch & RM= Stream0311,Reach-1,1155
     621    1034    1420     947    1890    3772    3299
Boundary for River Rch & Prof#=Stream0311,Reach-1,1
Up Type=0
Dn Type=3
Dn Slope=0.005
Boundary for River Rch & Prof#=Stream0311,Reach-1,2
Up Type=0
Dn Type=3
Dn Slope=0.005
Boundary for River Rch & Prof#=Stream0311,Reach-1,3
Up Type=0
Dn Type=3
Dn Slope=0.005
Boundary for River Rch & Prof#=Stream0311,Reach-1,4
Up Type=0
Dn Type=3
Dn Slope=0.005
Boundary for River Rch & Prof#=Stream0311,Reach-1,5
Up Type=0
Dn Type=3
Dn Slope=0.005
Boundary for River Rch & Prof#=Stream0311,Reach-1,6
Up Type=0
Dn Type=3
Dn Slope=0.005
Boundary for River Rch & Prof#=Stream0311,Reach-1,7
Up Type=0
Dn Type=3
Dn Slope=0.005

--- Stream0311.g01 (geometry) ---

Geom Title=Existing Conditions

River Reach=Stream0311,Reach-1
Reach XY= 30
      1859875.00     13934225.00      1859918.85     13934268.06
      1859931.04     13934273.73      1859954.89     13934275.46
      1859977.23     13934269.67      1860026.76     13934229.25
      1860069.17     13934222.59      1860085.06     13934214.39
      1860111.77     13934188.67      1860123.01     13934169.33
      1860125.40     13934040.16      1860130.46     13934022.54
      1860141.42     13934008.20      1860204.79     13933944.59
      1860226.46     13933928.54      1860249.89     13933924.73
      1860355.11     13933925.06      1860381.47     13933917.30
      1860402.19     13933898.96      1860419.25     13933877.55
      1860427.47     13933830.88      1860433.03     13933818.64
      1860451.10     13933797.71      1860472.30     13933780.36
      1860494.89     13933774.94      1860619.06     13933772.73
      1860634.65     13933764.15      1860668.94     13933733.13
      1860685.48     13933726.17      1860825.00     13933725.00

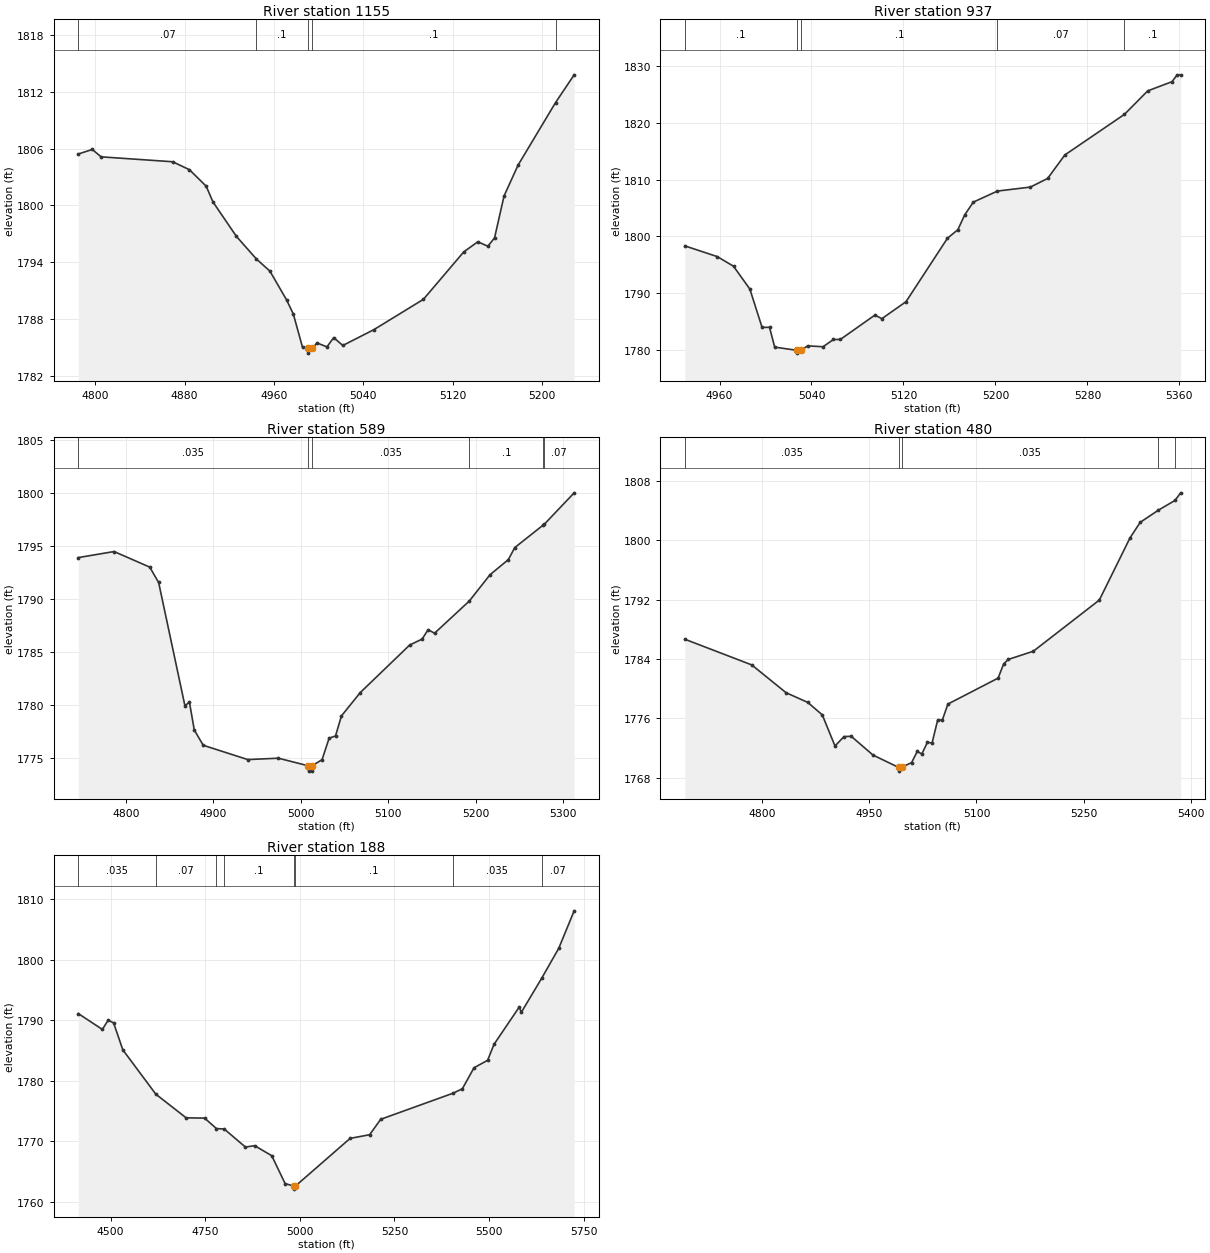
Type RM Length L Ch R = 1,1155,218,218,218
BEGIN DESCRIPTION:
Stream0311 3.0
END DESCRIPTION:
XS GIS Cut Line= 2
      1860105.86     13934441.95      1859859.01     13934072.78
#Sta/Elev= 30
  4784.8 1805.44  4797.3 1805.92  4805.2 1805.14  4869.3 1804.62  4884.3 1803.78
  4899.3 1802.04  4905.4 1800.37  4926.4 1796.73  4944.3 1794.34  4956.4 1793.06
  4971.4 1790.00  4977.4 1788.51  4985.6 1785.01  4990.4 1784.89  4990.7 1784.39
  4994.4 1784.89  4998.5 1785.47  5007.5 1785.05  5013.5 1786.03  5021.7 1785.20
  5049.5 1786.87  5093.9 1790.08  5130.0 1795.09  5142.6 1796.16  5151.6 1795.69
  5157.6 1796.57  5166.1 1801.00  5178.6 1804.25  5212.2 1810.87  5228.9 1813.81
#Mann=5,-1,0
  4784.8    0.07       0  4944.3     0.1       0  4990.4    0.05       0
  4994.4     0.1       0  5212.2    0.07       0
Bank Sta=4990.4,4994.4
Exp/Cntr=0.3,0.1

Type RM Length L Ch R = 1,937,348,348,348
BEGIN DESCRIPTION:
Stream0311 2.0
END DESCRIPTION:
XS GIS Cut Line= 3
      1860175.00     13934175.00      1860125.00     13934125.00
      1859824.98     13933924.98
#Sta/Elev= 30
  4929.8 1798.31  4958.1 1796.41  4972.2 1794.71  4986.4 1790.68  4997.0 1783.93
  5003.5 1783.93  5008.0 1780.44  5027.1 1779.88  5027.3 1779.38  5031.1 1779.88
  5036.6 1780.66  5050.1 1780.51  5059.1 1781.79  5065.1 1781.79  5095.2 1786.10
  5101.2 1785.46  5122.2 1788.45  5158.3 1799.66  5167.3 1801.15  5173.3 1803.78
  5180.8 1806.03  5201.8 1807.98  5230.4 1808.68  5245.4 1810.20  5260.4 1814.35
  5312.2 1821.51  5332.5 1825.66  5353.6 1827.28  5358.1 1828.49  5361.1 1828.49
#Mann=5,-1,0
  4929.8     0.1       0  5027.1    0.05       0  5031.1     0.1       0
  5201.8    0.07       0  5312.2     0.1       0
Bank Sta=5027.1,5031.1
Exp/Cntr=0.3,0.1

Type RM Length L Ch R = 1,589,109,109,109
BEGIN DESCRIPTION:
Mapping XS ee6195e6
END DESCRIPTION:
XS GIS Cut Line= 3
      1860384.97     13934175.07      1860330.00     13933901.66
      1860119.76     13933704.06
#Sta/Elev= 30
  4745.4 1793.92  4786.3 1794.49  4827.1 1793.02  4837.3 1791.57  4867.4 1779.93
  4872.5 1780.29  4878.1 1777.65  4888.3 1776.21  4939.3 1774.86  4974.3 1774.99
  5008.7 1774.27  5008.9 1773.77  5012.4 1773.77  5012.7 1774.27  5024.3 1774.85
  5032.4 1776.88  5039.7 1777.09  5046.5 1778.98  5068.0 1781.18  5124.6 1785.67
  5138.8 1786.23  5145.7 1787.12  5153.0 1786.78  5192.8 1789.82  5216.5 1792.30
  5237.5 1793.73  5244.8 1794.86  5277.7 1797.01  5278.8 1797.08  5312.8 1800.03
#Mann=6,-1,0
  4745.4   0.035       0  5008.7   0.035       0  5012.7   0.035       0
  5192.8     0.1       0  5277.7   0.035       0  5278.8    0.07       0
Bank Sta=5008.7,5012.7
Exp/Cntr=0.3,0.1

Type RM Length L Ch R = 1,480,292,292,292
BEGIN DESCRIPTION:
Stream0311 1.0
END DESCRIPTION:
XS GIS Cut Line= 3
      1860475.00     13934174.99      1860425.00     13933875.00
      1860125.03     13933625.03
#Sta/Elev= 30
  4691.4 1786.67  4785.2 1783.20  4833.3 1779.45  4863.7 1778.14  4884.0 1776.46
  4901.8 1772.26  4914.4 1773.53  4924.6 1773.57  4955.0 1771.04  4991.0 1769.37
  4991.2 1768.87  4995.0 1769.37  5009.2 1770.03  5017.0 1771.52  5023.5 1771.19
  5031.3 1772.77  5037.8 1772.66  5045.6 1775.75  5052.2 1775.77  5060.0 1777.92
  5130.3 1781.42  5138.1 1783.34  5144.6 1783.94  5179.7 1785.05  5272.1 1791.95
  5315.1 1800.34  5329.4 1802.44  5355.0 1804.09  5378.2 1805.40  5386.0 1806.42
#Mann=5,-1,0
  4691.4   0.035       0  4991.0   0.035       0  4995.0   0.035       0
  5355.0    0.07       0  5378.2     0.1       0
Bank Sta=4991,4995
Exp/Cntr=0.3,0.1

Type RM Length L Ch R = 1,188,0,0,0
BEGIN DESCRIPTION:
Stream0311 0.0
END DESCRIPTION:
XS GIS Cut Line= 4
      1860486.32     13934298.23      1860673.39     13933825.82
      1860596.42     13933617.36      1860078.82     13933355.25
#Sta/Elev= 30
  4414.6 1791.09  4478.1 1788.48  4493.4 1790.00  4507.8 1789.56  4532.1 1785.12
  4619.4 1777.79  4699.6 1773.88  4748.3 1773.84  4779.6 1772.11  4800.3 1772.03
  4856.4 1769.05  4880.6 1769.29  4925.8 1767.63  4961.1 1763.03  4984.2 1762.61
  4984.5 1762.11  4988.2 1762.61  5133.0 1770.49  5184.5 1771.09  5213.8 1773.64
  5404.3 1777.93  5429.6 1778.68  5460.4 1782.15  5496.4 1783.38  5513.1 1786.00
  5579.9 1792.17  5585.5 1791.31  5638.9 1796.89  5684.5 1801.89  5725.1 1808.06
#Mann=8,-1,0
  4414.6   0.035       0  4619.4    0.07       0  4779.6   0.035       0
  4800.3     0.1       0  4984.2    0.05       0  4988.2     0.1       0
  5404.3   0.035       0  5638.9    0.07       0
Bank Sta=4984.2,4988.2
Exp/Cntr=0.3,0.1

Chan Stop Cuts=-1