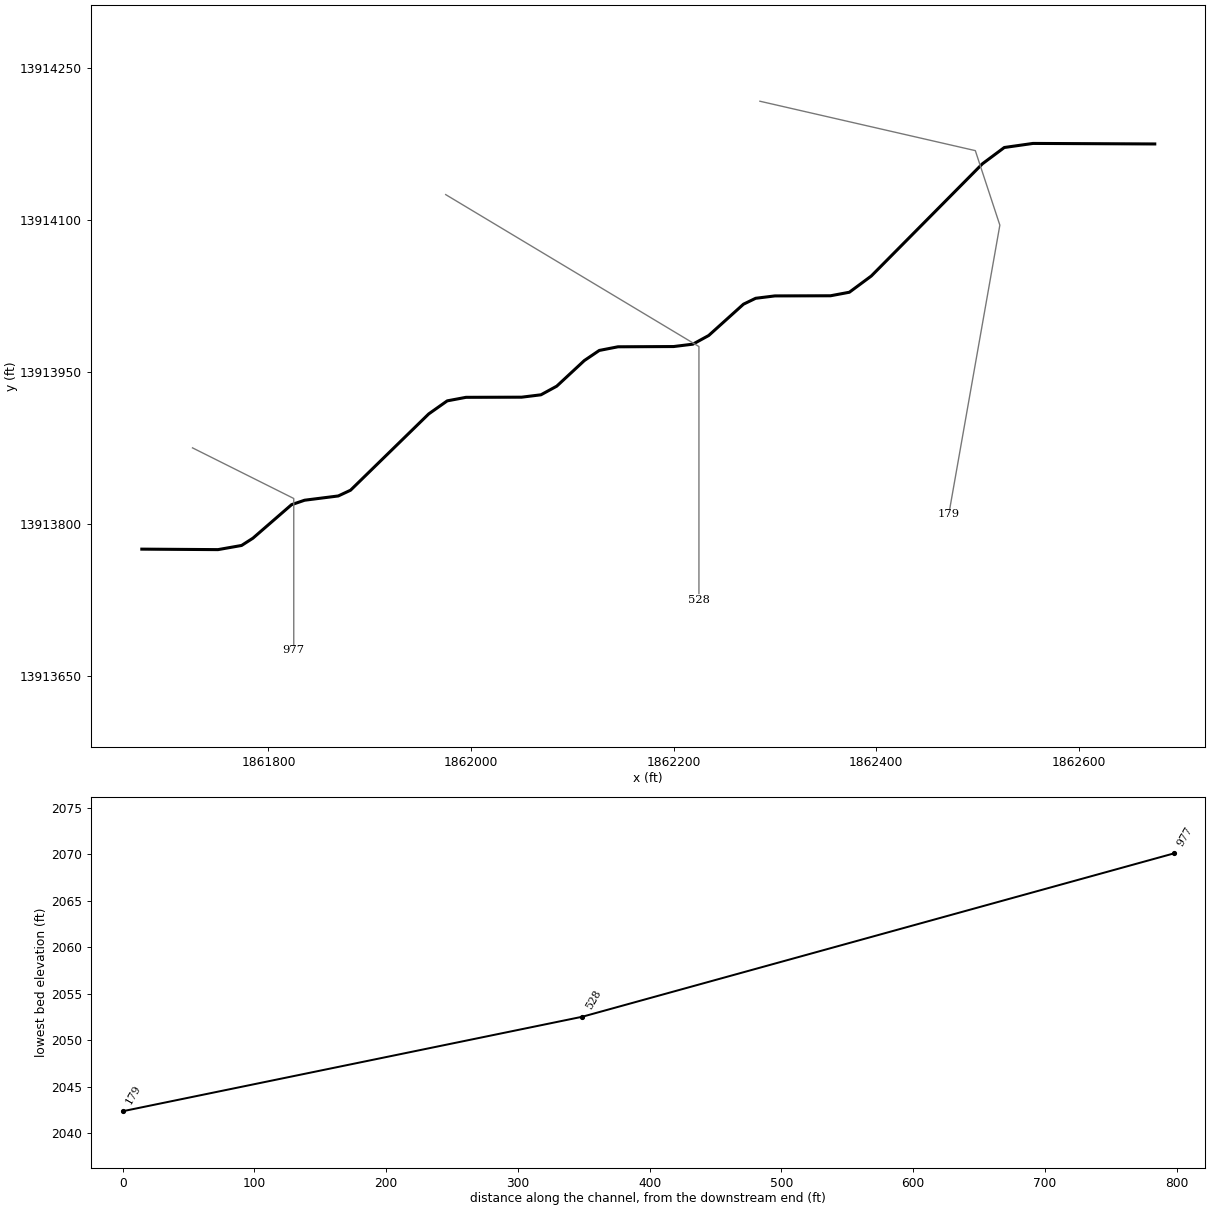
--- Stream0313.prj (project) ---

Proj Title=Stream0313 Base Level Engineering
Current Plan=p01
Default Exp/Contr=0.3,0.1
English Units
Geom File=g01
Flow File=f01
Plan File=p01
Y Axis Title=Elevation
X Axis Title(PF)=Main Channel Distance
X Axis Title(XS)=Station
BEGIN DESCRIPTION:
Stream0313
END DESCRIPTION:
DSS Export Rating Curves= 0
DSS Export Rating Curve Sorted= 0
DSS Export Volume Flow Curves= 0
DXF OffsetX= 0
DXF OffsetY= 0
DXF ScaleX= 1
DXF ScaleY= 10

--- Stream0313.p01 (plan) ---

Plan Title=Multiple Run
Short Identifier=Multiple
Geom File=g01
Flow File=f01
Subcritical Flow
K Sum by GR= 0
Std Step Tol= 0.01
Critical Tol= 0.01
Num of Std Step Trials= 20
Max Error Tol= 0.3
Flow Tol Ratio= 0.001
Split Flow NTrial= 30
Split Flow Tol= 0.02
Split Flow Ratio= 0.02
Log Output Level= 0
Friction Slope Method= 1
Unsteady Friction Slope Method= 2
Unsteady Bridges Friction Slope Method= 1
Parabolic Critical Depth
Global Vel Dist=  1 , 1 , 1
Global Log Level= 0
CheckData=True
Encroach Param= -1, 0, 0, 0
BEGIN DESCRIPTION:
Multiple Run
END DESCRIPTION:

--- Stream0313.f01 (steady flow) ---

Flow Title=Multiple
Number of Profiles=7
Profile Names=10-year,25-year,50-year,1pct_min,100-year,1pct_plu,500-year
River Rch & RM= Stream0313,Reach-1,977
     235     361     470     298     594    1186     934
Boundary for River Rch & Prof#=Stream0313,Reach-1,1
Up Type=0
Dn Type=3
Dn Slope=0.005
Boundary for River Rch & Prof#=Stream0313,Reach-1,2
Up Type=0
Dn Type=3
Dn Slope=0.005
Boundary for River Rch & Prof#=Stream0313,Reach-1,3
Up Type=0
Dn Type=3
Dn Slope=0.005
Boundary for River Rch & Prof#=Stream0313,Reach-1,4
Up Type=0
Dn Type=3
Dn Slope=0.005
Boundary for River Rch & Prof#=Stream0313,Reach-1,5
Up Type=0
Dn Type=3
Dn Slope=0.005
Boundary for River Rch & Prof#=Stream0313,Reach-1,6
Up Type=0
Dn Type=3
Dn Slope=0.005
Boundary for River Rch & Prof#=Stream0313,Reach-1,7
Up Type=0
Dn Type=3
Dn Slope=0.005

--- Stream0313.g01 (geometry) ---

Geom Title=Existing Conditions
Program Version=4.10

River Reach=Stream0313      ,Reach-1
Reach XY= 30
        1861675.       13913775.       1861750.2     13913774.52
       1861773.5     13913778.63      1861784.67     13913785.79
      1861822.82     13913818.89      1861835.71     13913823.29
      1861868.96      13913827.5      1861881.05     13913833.16
      1861958.26     13913908.51       1861976.5     13913921.38
      1861995.05     13913924.87        1862050.     13913925.01
      1862069.02     13913927.36      1862084.63     13913935.89
      1862111.87     13913961.18       1862126.6     13913971.15
       1862145.1     13913974.76        1862200.       13913975.
      1862219.03     13913977.35      1862234.63     13913985.89
      1862268.96     13914016.81      1862280.98     13914022.64
        1862300.     13914024.99      1862354.95     13914025.13
       1862373.5     13914028.61      1862395.15     13914044.63
      1862504.84      13914155.4      1862526.45      13914171.5
      1862554.79     13914175.52        1862675.       13914175.

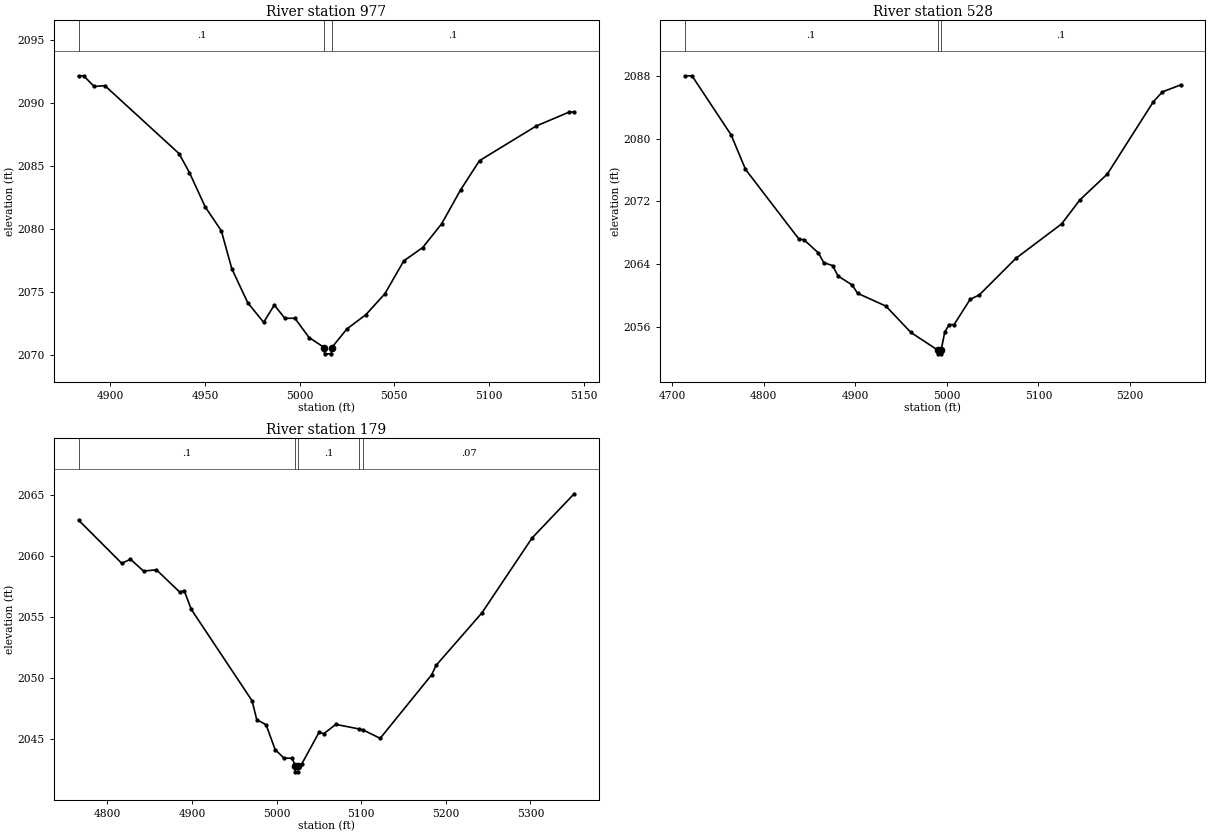
Type RM Length L Ch R = 1 ,977     ,449,449,449
BEGIN DESCRIPTION:
Stream0313 2.0
END DESCRIPTION:
XS GIS Cut Line= 3
      1861725.04     13913874.98        1861825.       13913825.
        1861825.     13913674.95
#Sta/Elev= 30
  4883.2 2092.13  4885.9 2092.13  4891.5 2091.28  4897.1 2091.35  4936.3 2085.96
  4941.8 2084.45  4950.2 2081.71  4958.6 2079.85  4964.2 2076.82  4972.6 2074.13
    4981 2072.58  4986.6 2073.95  4992.2  2072.9  4997.5  2072.9    5005 2071.37
    5013 2070.58  5013.2 2070.08  5016.7 2070.08    5017 2070.58    5025 2072.06
    5035 2073.19    5045 2074.84    5055 2077.45    5065 2078.51    5075 2080.39
    5085 2083.08    5095  2085.4    5125 2088.15  5142.5 2089.26    5145 2089.26
#Mann= 3 ,-1 , 0
  4883.2      .1       0    5013     .05       0    5017      .1       0
Bank Sta=5013,5017
XS Rating Curve= 0 ,0
Exp/Cntr=0.3,0.1

Type RM Length L Ch R = 1 ,528     ,349,349,349
BEGIN DESCRIPTION:
Stream0313 1.0
END DESCRIPTION:
XS GIS Cut Line= 3
        1861975.       13914125.        1862225.       13913975.
        1862225.     13913725.04
#Sta/Elev= 30
  4713.9 2088.03  4721.7 2088.01  4764.4 2080.46    4780 2076.08  4838.3 2067.18
  4844.1 2067.07  4859.7 2065.39  4865.5 2064.16  4875.2 2063.78  4881.1 2062.46
  4896.6  2061.3  4902.4 2060.25  4933.5  2058.6  4960.7 2055.24  4989.8 2053.01
  4990.1 2052.51  4993.6 2052.51  4993.8 2053.01  4997.7  2055.3  5002.5 2056.24
  5007.9 2056.24  5025.4 2059.47  5035.4 2060.03  5075.4 2064.71  5125.4 2069.11
  5145.4 2072.18  5175.4 2075.49  5225.4 2084.68  5235.4 2085.97  5255.4 2086.86
#Mann= 3 ,-1 , 0
  4713.9      .1       0  4989.8     .05       0  4993.8      .1       0
Bank Sta=4989.8,4993.8
XS Rating Curve= 0 ,0
Exp/Cntr=0.3,0.1

Type RM Length L Ch R = 1 ,179     ,0,0,0
BEGIN DESCRIPTION:
Stream0313 0.0
END DESCRIPTION:
XS GIS Cut Line= 4
      1862285.19     13914217.18      1862497.85     13914168.41
      1862522.06     13914094.85      1862471.64     13913809.29
#Sta/Elev= 30
    4766 2062.93  4817.1 2059.39  4827.4 2059.73  4842.8 2058.76  4858.1 2058.86
  4885.7 2057.03  4890.8 2057.17  4899.2 2055.63    4971 2048.16  4976.6 2046.61
  4987.6 2046.19  4998.3 2044.16  5008.8 2043.46  5018.6 2043.45  5021.8 2042.84
  5022.1 2042.34  5025.6 2042.34  5025.8 2042.84  5029.9    2043  5050.4  2045.6
  5055.6 2045.45    5070 2046.22  5097.3 2045.85  5102.1 2045.77  5122.4 2045.08
  5183.3 2050.28  5188.4 2051.04  5242.6 2055.34  5301.8 2061.46  5351.6 2065.08
#Mann= 5 ,-1 , 0
    4766      .1       0  5021.8     .05       0  5025.8      .1       0
  5097.3      .1       0  5102.1     .07       0
Bank Sta=5021.8,5025.8
XS Rating Curve= 0 ,0
Exp/Cntr=0.3,0.1

Chan Stop Cuts=-1
Use User Specified Reach Order=0
Composite Channel Slope=5