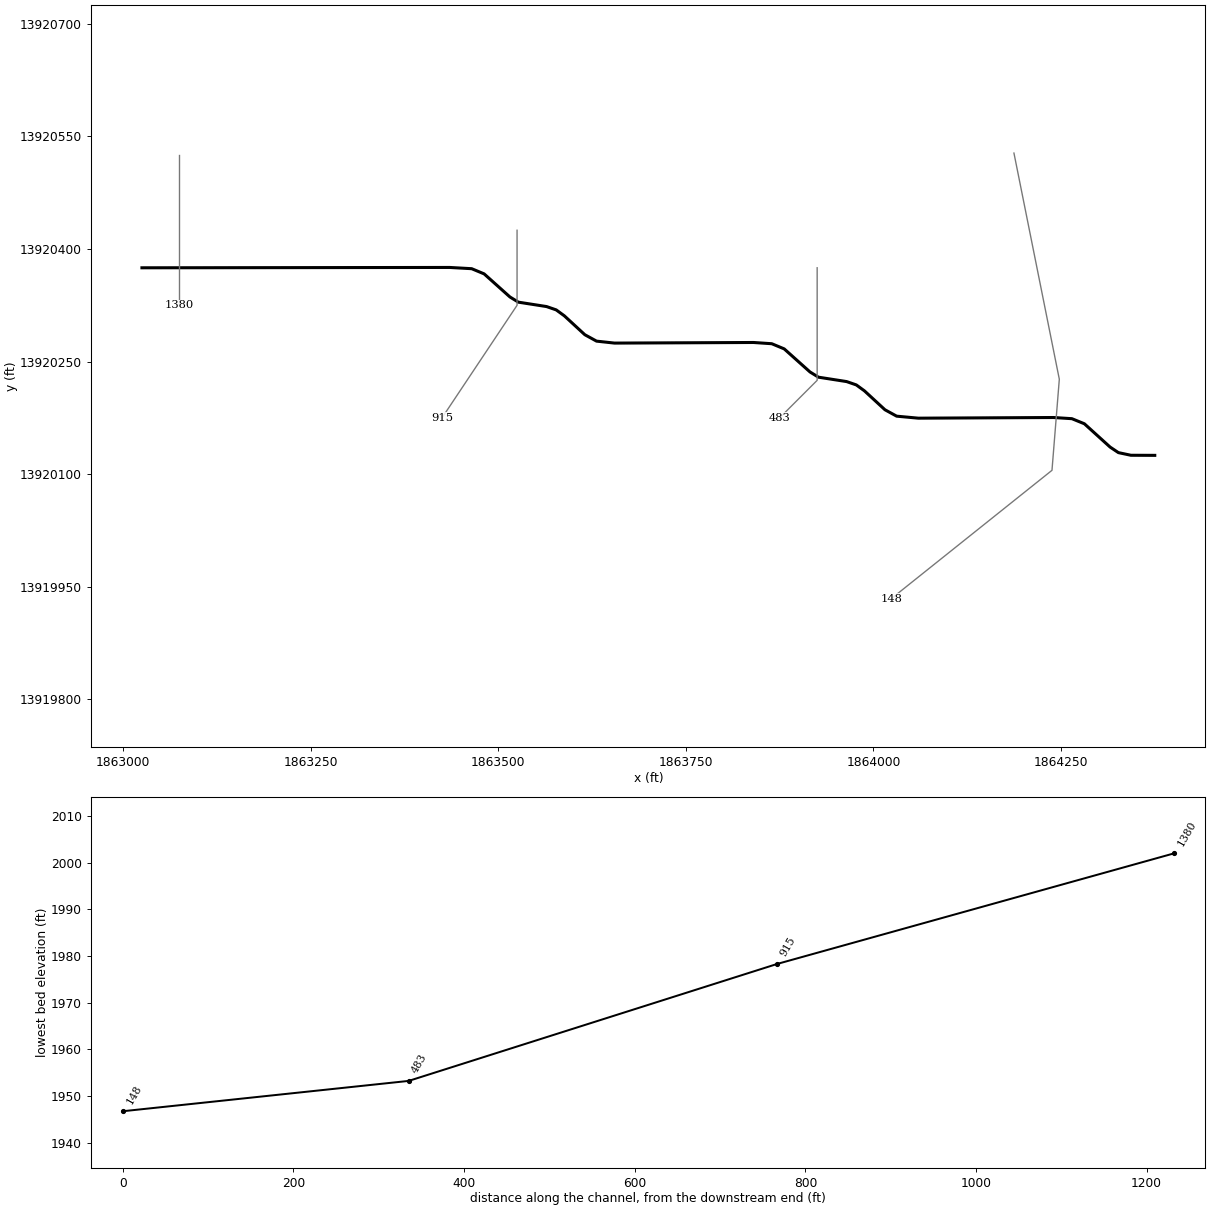
--- Stream0314.prj (project) ---

Proj Title=Stream0314 Base Level Engineering
Current Plan=p01
Default Exp/Contr=0.3,0.1
English Units
Geom File=g01
Flow File=f01
Plan File=p01
Y Axis Title=Elevation
X Axis Title(PF)=Main Channel Distance
X Axis Title(XS)=Station
BEGIN DESCRIPTION:
Stream0314
END DESCRIPTION:
DSS Export Rating Curves= 0
DSS Export Rating Curve Sorted= 0
DSS Export Volume Flow Curves= 0
DXF OffsetX= 0
DXF OffsetY= 0
DXF ScaleX= 1
DXF ScaleY= 10

--- Stream0314.p01 (plan) ---

Plan Title=Multiple Run
Short Identifier=Multiple
Geom File=g01
Flow File=f01
Subcritical Flow
K Sum by GR= 0
Std Step Tol= 0.01
Critical Tol= 0.01
Num of Std Step Trials= 20
Max Error Tol= 0.3
Flow Tol Ratio= 0.001
Split Flow NTrial= 30
Split Flow Tol= 0.02
Split Flow Ratio= 0.02
Log Output Level= 0
Friction Slope Method= 1
Unsteady Friction Slope Method= 2
Unsteady Bridges Friction Slope Method= 1
Parabolic Critical Depth
Global Vel Dist=  1 , 1 , 1
Global Log Level= 0
CheckData=True
Encroach Param= -1, 0, 0, 0
BEGIN DESCRIPTION:
Multiple Run
END DESCRIPTION:

--- Stream0314.f01 (steady flow) ---

Flow Title=Multiple
Program Version=4.10
Number of Profiles= 7
Profile Names=10-year,25-year,50-year,1pct_min,100-year,1pct_plu,500-year
River Rch & RM=Stream0314,Reach-1         ,1380
     354     564     752     488     974    1944    1605
Boundary for River Rch & Prof#=Stream0314,Reach-1         , 1
Up Type= 0
Dn Type= 3
Dn Slope=0.02
Boundary for River Rch & Prof#=Stream0314,Reach-1         , 2
Up Type= 0
Dn Type= 3
Dn Slope=0.02
Boundary for River Rch & Prof#=Stream0314,Reach-1         , 3
Up Type= 0
Dn Type= 3
Dn Slope=0.02
Boundary for River Rch & Prof#=Stream0314,Reach-1         , 4
Up Type= 0
Dn Type= 3
Dn Slope=0.02
Boundary for River Rch & Prof#=Stream0314,Reach-1         , 5
Up Type= 0
Dn Type= 3
Dn Slope=0.02
Boundary for River Rch & Prof#=Stream0314,Reach-1         , 6
Up Type= 0
Dn Type= 3
Dn Slope=0.02
Boundary for River Rch & Prof#=Stream0314,Reach-1         , 7
Up Type= 0
Dn Type= 3
Dn Slope=0.02
DSS Import GetInterval= 0
DSS Import GetPeak= 0
DSS Import FillOption= 0

--- Stream0314.g01 (geometry) ---

Geom Title=Existing Conditions

River Reach=Stream0314,Reach-1
Reach XY= 30
      1863025.00     13920375.00      1863435.19     13920375.46
      1863464.50     13920373.80      1863481.08     13920366.91
      1863515.47     13920336.14      1863526.74     13920329.19
      1863564.31     13920323.33      1863577.18     13920318.88
      1863588.04     13920310.96      1863615.33     13920285.80
      1863630.93     13920277.24      1863654.85     13920274.64
      1863840.18     13920275.44      1863864.50     13920273.80
      1863881.08     13920266.91      1863915.47     13920236.14
      1863926.74     13920229.19      1863964.31     13920223.33
      1863977.18     13920218.88      1863988.04     13920210.96
      1864015.33     13920185.80      1864030.93     13920177.24
      1864059.82     13920174.56      1864240.18     13920175.44
      1864264.54     13920173.88      1864281.16     13920167.11
      1864315.44     13920136.06      1864326.51     13920128.65
      1864343.20     13920125.12      1864375.00     13920125.00

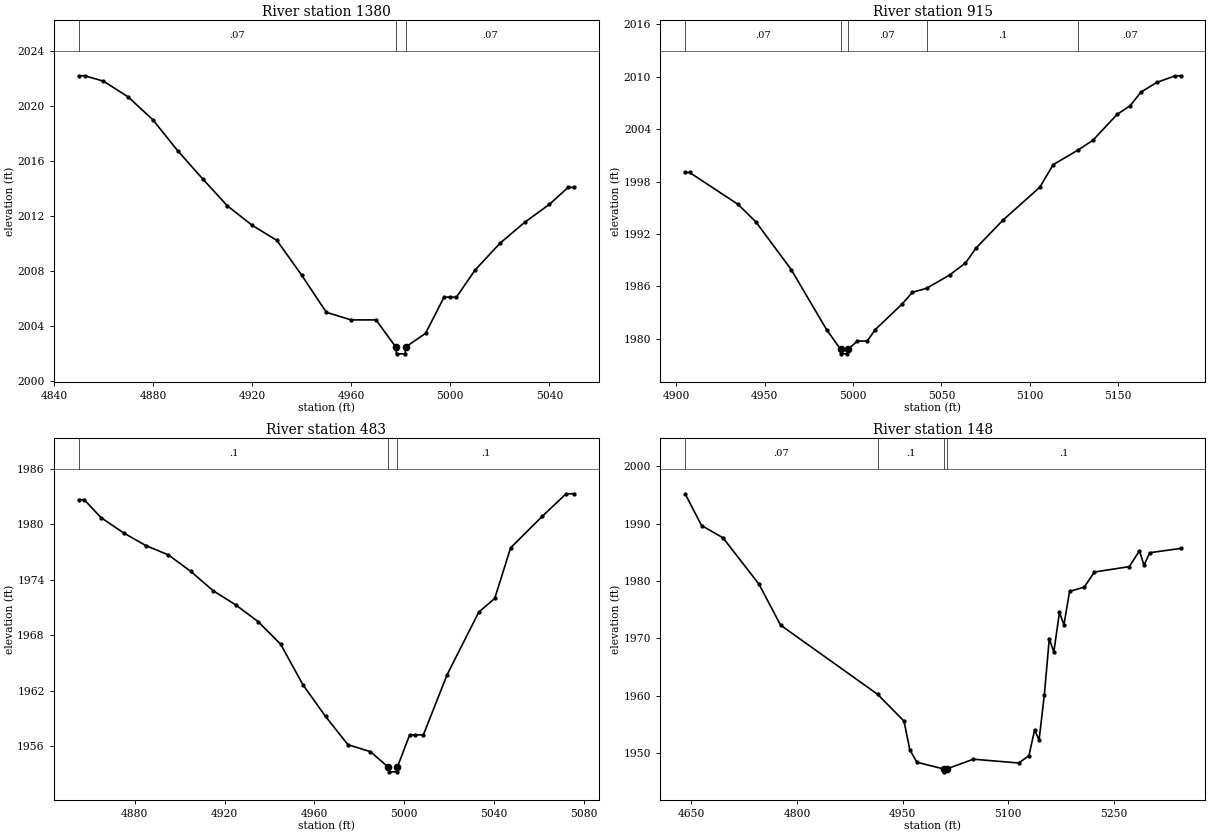
Type RM Length L Ch R = 1,1380,465,465,465
BEGIN DESCRIPTION:
Stream0314 3.0
END DESCRIPTION:
XS GIS Cut Line= 3
      1863075.00     13920525.00      1863075.00     13920375.00
      1863075.00     13920325.00
#Sta/Elev= 28
  4850.0 2022.19  4852.5 2022.19  4860.0 2021.80  4870.0 2020.65  4880.0 2018.98
  4890.0 2016.73  4900.0 2014.70  4910.0 2012.73  4920.0 2011.31  4930.0 2010.21
  4940.0 2007.68  4950.0 2004.97  4960.0 2004.42  4970.0 2004.42  4978.0 2002.45
  4978.3 2001.95  4981.8 2001.95  4982.0 2002.45  4990.0 2003.44  4997.5 2006.08
  5000.0 2006.08  5002.5 2006.08  5010.0 2008.05  5020.0 2009.99  5030.0 2011.52
  5040.0 2012.83  5047.5 2014.06  5050.0 2014.06
#Mann=3,-1,0
  4850.0    0.07       0  4978.0    0.05       0  4982.0    0.07       0
Bank Sta=4978,4982
Exp/Cntr=0.3,0.1

Type RM Length L Ch R = 1,915,432,432,432
BEGIN DESCRIPTION:
Stream0314 2.0
END DESCRIPTION:
XS GIS Cut Line= 3
      1863525.00     13920425.04      1863525.00     13920325.00
      1863425.01     13920175.02
#Sta/Elev= 30
  4905.0 1999.05  4907.5 1999.05  4935.0 1995.39  4945.0 1993.40  4965.0 1987.94
  4985.0 1981.07  4993.0 1978.79  4993.3 1978.29  4996.8 1978.29  4997.0 1978.79
  5002.5 1979.75  5008.0 1979.75  5012.6 1981.07  5027.6 1983.96  5033.6 1985.33
  5041.7 1985.80  5054.6 1987.31  5063.6 1988.69  5069.6 1990.40  5084.7 1993.57
  5105.7 1997.37  5113.2 1999.94  5127.5 2001.64  5135.7 2002.73  5149.3 2005.68
  5156.8 2006.70  5162.8 2008.23  5171.8 2009.35  5182.3 2010.11  5185.3 2010.11
#Mann=5,-1,0
  4905.0    0.07       0  4993.0    0.05       0  4997.0    0.07       0
  5041.7     0.1       0  5127.5    0.07       0
Bank Sta=4993,4997
Exp/Cntr=0.3,0.1

Type RM Length L Ch R = 1,483,335,335,335
BEGIN DESCRIPTION:
Stream0314 1.0
END DESCRIPTION:
XS GIS Cut Line= 3
      1863925.00     13920375.04      1863925.00     13920225.00
      1863874.97     13920174.97
#Sta/Elev= 29
  4855.0 1982.64  4857.5 1982.64  4865.0 1980.70  4875.0 1979.06  4885.0 1977.68
  4895.0 1976.68  4905.0 1974.89  4915.0 1972.80  4925.0 1971.28  4935.0 1969.47
  4945.0 1967.04  4955.0 1962.63  4965.0 1959.24  4975.0 1956.18  4985.0 1955.43
  4993.0 1953.75  4993.3 1953.25  4996.8 1953.25  4997.0 1953.75  5002.5 1957.24
  5005.0 1957.24  5008.6 1957.24  5019.2 1963.75  5033.3 1970.50  5040.4 1971.98
  5047.5 1977.45  5061.6 1980.85  5072.2 1983.28  5075.8 1983.28
#Mann=3,-1,0
  4855.0     0.1       0  4993.0    0.05       0  4997.0     0.1       0
Bank Sta=4993,4997
Exp/Cntr=0.3,0.1

Type RM Length L Ch R = 1,148,0,0,0
BEGIN DESCRIPTION:
Stream0314 0.0
END DESCRIPTION:
XS GIS Cut Line= 4
      1864187.29     13920527.89      1864247.77     13920226.48
      1864237.99     13920105.06      1864023.83     13919934.04
#Sta/Elev= 30
  4641.3 1995.20  4664.7 1989.67  4695.2 1987.52  4746.2 1979.44  4776.8 1972.32
  4914.5 1960.27  4952.0 1955.59  4960.2 1950.62  4970.3 1948.43  5008.4 1947.26
  5008.7 1946.76  5012.4 1947.26  5050.5 1948.96  5114.9 1948.30  5129.3 1949.58
  5137.3 1954.04  5143.7 1952.33  5151.1 1960.10  5158.2 1969.98  5164.6 1967.63
  5172.6 1974.52  5179.0 1972.39  5187.0 1978.20  5207.8 1978.94  5222.2 1981.57
  5271.8 1982.51  5286.2 1985.28  5292.6 1982.72  5300.7 1984.93  5344.6 1985.68
#Mann=4,-1,0
  4641.3    0.07       0  4914.5     0.1       0  5008.4    0.05       0
  5012.4     0.1       0
Bank Sta=5008.4,5012.4
Exp/Cntr=0.3,0.1

Chan Stop Cuts=-1