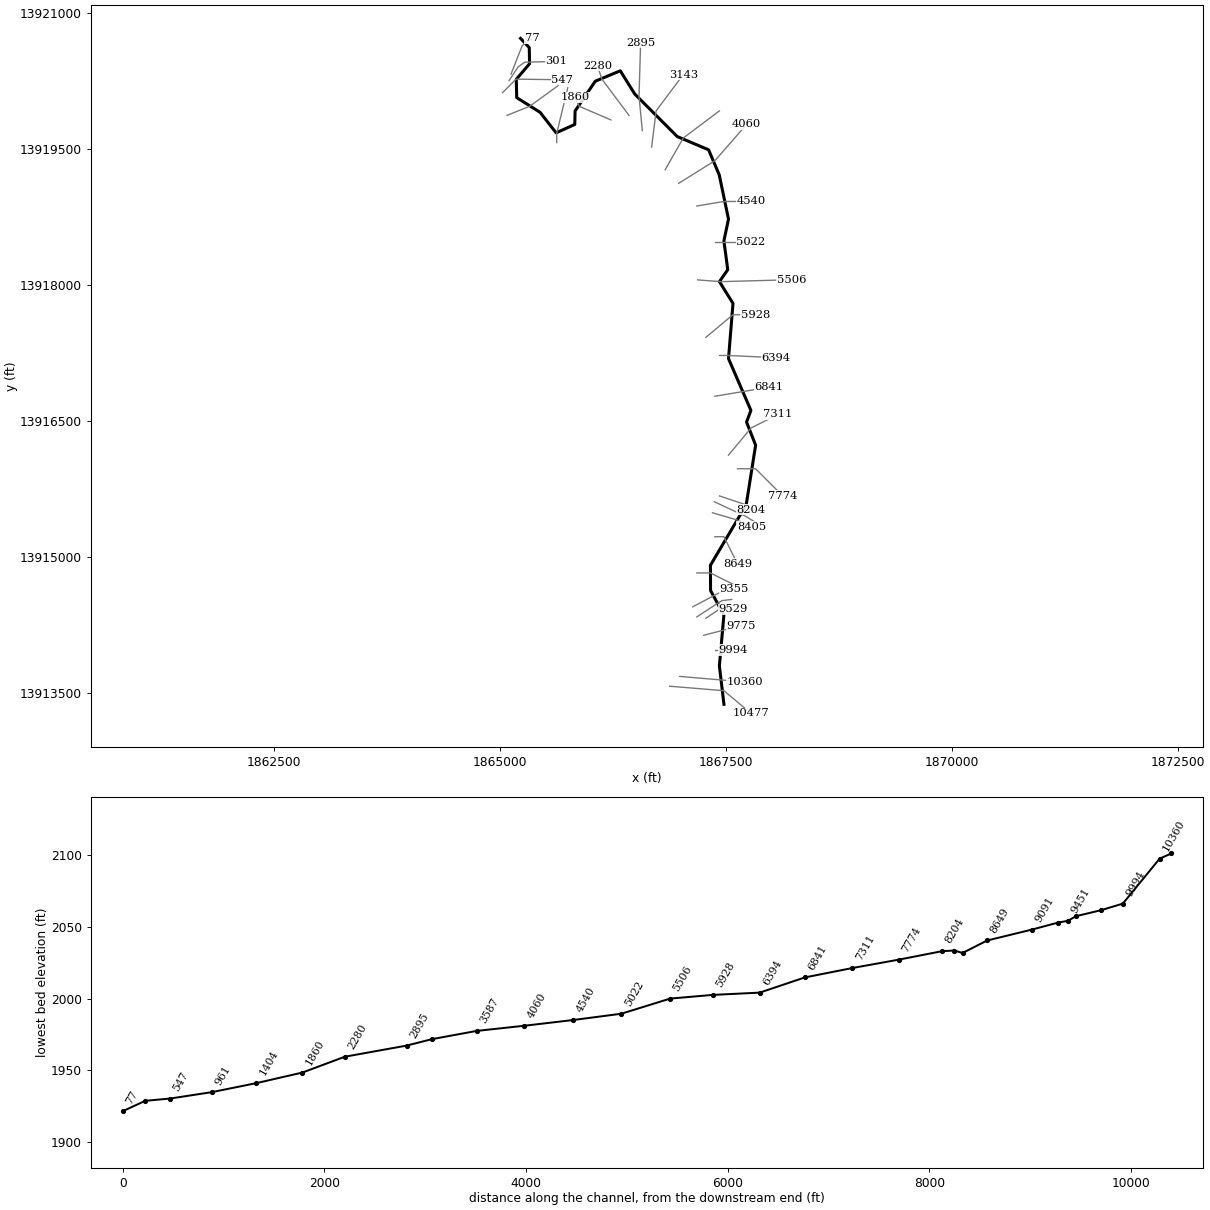
--- Stream0315.prj (project) ---

Proj Title=Stream0315 Base Level Engineering
Current Plan=p01
Default Exp/Contr=0.3,0.1
English Units
Geom File=g01
Flow File=f01
Plan File=p01
Y Axis Title=Elevation
X Axis Title(PF)=Main Channel Distance
X Axis Title(XS)=Station
BEGIN DESCRIPTION:
Stream0315
END DESCRIPTION:
DSS Export Rating Curves= 0
DSS Export Rating Curve Sorted= 0
DSS Export Volume Flow Curves= 0
DXF OffsetX= 0
DXF OffsetY= 0
DXF ScaleX= 1
DXF ScaleY= 10

--- Stream0315.p01 (plan) ---

Plan Title=Multiple Run
Short Identifier=Multiple
Geom File=g01
Flow File=f01
Subcritical Flow
K Sum by GR= 0
Std Step Tol= 0.01
Critical Tol= 0.01
Num of Std Step Trials= 20
Max Error Tol= 0.3
Flow Tol Ratio= 0.001
Split Flow NTrial= 30
Split Flow Tol= 0.02
Split Flow Ratio= 0.02
Log Output Level= 0
Friction Slope Method= 1
Unsteady Friction Slope Method= 2
Unsteady Bridges Friction Slope Method= 1
Parabolic Critical Depth
Global Vel Dist=  1 , 1 , 1
Global Log Level= 0
CheckData=True
Encroach Param= -1, 0, 0, 0
BEGIN DESCRIPTION:
Multiple Run
END DESCRIPTION:

--- Stream0315.f01 (steady flow) ---

Flow Title=Multiple
Program Version=4.10
Number of Profiles= 7
Profile Names=10-year,25-year,50-year,1pct_min,100-year,1pct_plu,500-year
River Rch & RM=Stream0315,Reach-1         ,10477
     903    1528    2119    1423    2838    5663    5026
River Rch & RM=Stream0315,Reach-1         ,6841
    1617    2824    3999    2733    5454   10882   10028
River Rch & RM=Stream0315,Reach-1         ,1404
    1783    3129    4445    3047    6080   12130   11244
Boundary for River Rch & Prof#=Stream0315,Reach-1         , 1
Up Type= 0
Dn Type= 3
Dn Slope=0.01
Boundary for River Rch & Prof#=Stream0315,Reach-1         , 2
Up Type= 0
Dn Type= 3
Dn Slope=0.01
Boundary for River Rch & Prof#=Stream0315,Reach-1         , 3
Up Type= 0
Dn Type= 3
Dn Slope=0.01
Boundary for River Rch & Prof#=Stream0315,Reach-1         , 4
Up Type= 0
Dn Type= 3
Dn Slope=0.01
Boundary for River Rch & Prof#=Stream0315,Reach-1         , 5
Up Type= 0
Dn Type= 3
Dn Slope=0.01
Boundary for River Rch & Prof#=Stream0315,Reach-1         , 6
Up Type= 0
Dn Type= 3
Dn Slope=0.01
Boundary for River Rch & Prof#=Stream0315,Reach-1         , 7
Up Type= 0
Dn Type= 3
Dn Slope=0.01
DSS Import GetInterval= 0
DSS Import GetPeak= 0
DSS Import FillOption= 0

--- Stream0315.g01 (geometry) ---

Geom Title=Existing Conditions
Program Version=4.10

River Reach=Stream0315      ,Reach-1
Reach XY= 30
        1867475.       13913375.       1867424.6       13913800.
      1867474.48     13914359.78      1867327.07     13914630.86
      1867325.51     13914909.79      1867721.25     13915576.55
      1867825.45     13916235.19       1867725.1      13916490.4
      1867773.35     13916618.92      1867525.51     13917190.21
      1867575.24      13917800.1      1867424.86     13918040.36
      1867517.19     13918171.59      1867474.57     13918490.18
      1867525.45     13918730.18      1867422.87     13919219.12
      1867305.24     13919495.14      1866958.32     13919641.64
      1866488.26     13920111.35      1866328.42     13920367.21
      1866051.48     13920252.01      1865828.51     13919923.55
        1865825.       13919775.      1865618.67     13919682.34
      1865441.67     13919908.35      1865182.72     13920071.34
      1865178.13     13920273.37      1865325.04     13920444.98
      1865321.52     13920623.56        1865225.       13920725.

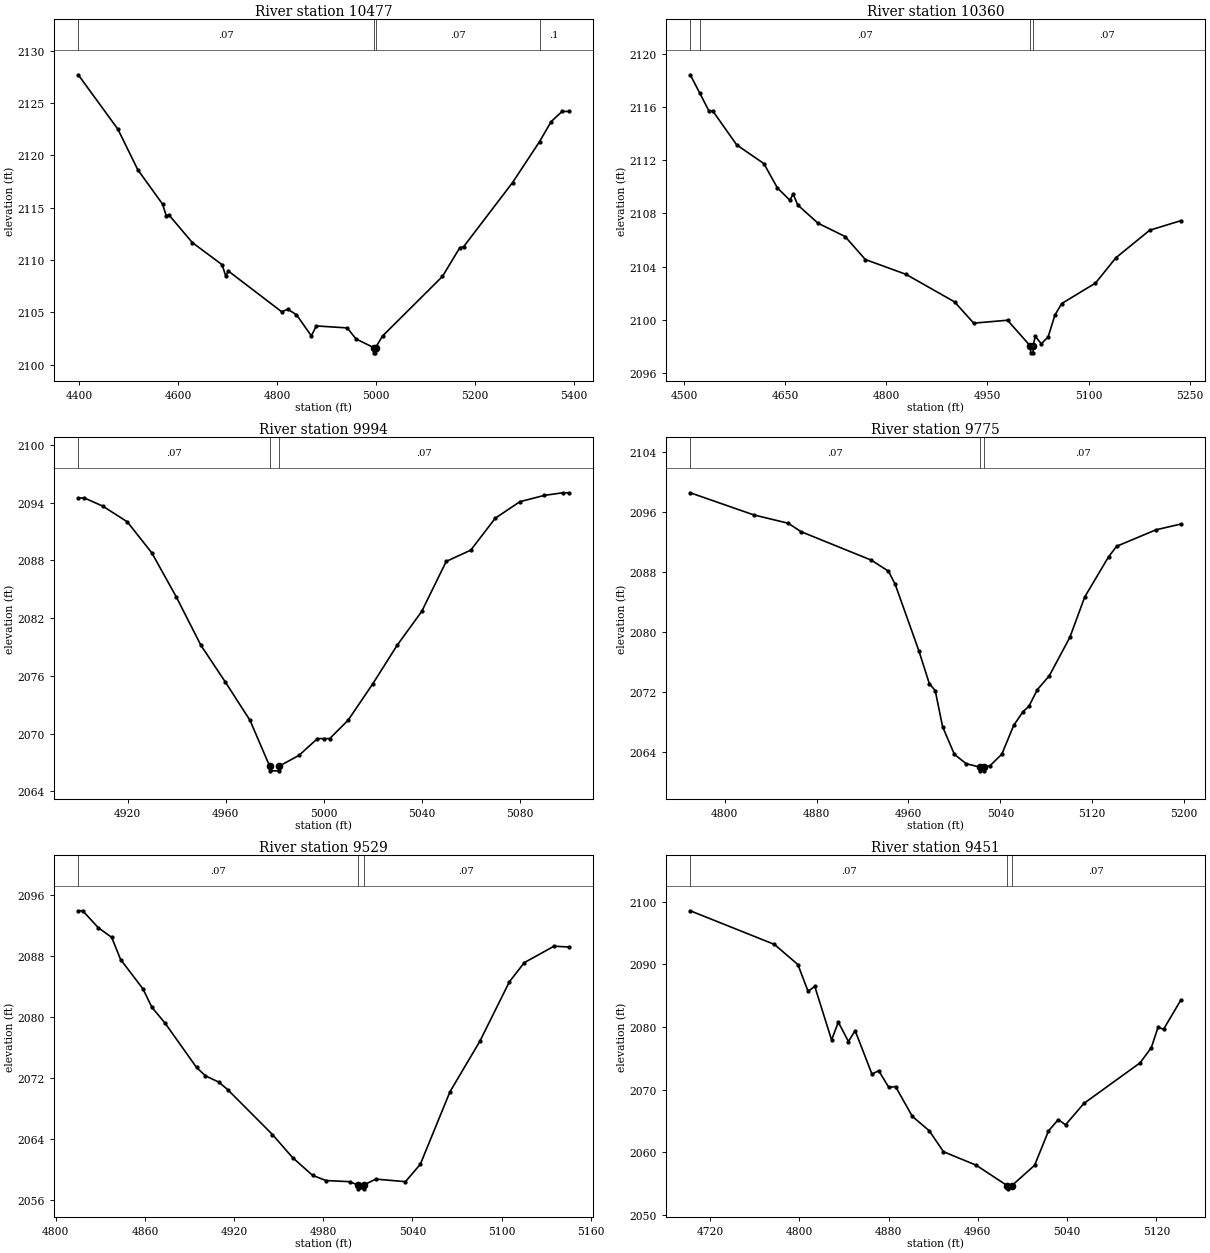
Type RM Length L Ch R = 1 ,10477   ,117,117,117
BEGIN DESCRIPTION:
Stream0315 23.0
END DESCRIPTION:
XS GIS Cut Line= 3
      1866875.04       13913575.        1867475.       13913525.
      1867775.04     13913274.97
#Sta/Elev= 30
  4397.5  2127.7  4477.7  2122.5  4517.9 2118.63    4568 2115.35  4575.6 2114.23
  4580.6 2114.33  4628.3 2111.67  4688.5 2109.56    4696 2108.45    4701 2108.96
  4808.9 2105.07  4821.4  2105.3    4839 2104.78  4869.1 2102.76  4879.1 2103.71
  4941.8 2103.52  4959.4 2102.47    4995 2101.64  4995.3 2101.14  4998.8 2101.14
    4999 2101.64  5013.2 2102.75  5134.3 2108.44  5169.4 2111.18  5177.2 2111.28
  5276.2 2117.41  5330.8 2121.32  5354.3 2123.23  5376.4  2124.2  5390.1  2124.2
#Mann= 4 ,-1 , 0
  4397.5     .07       0    4995     .05       0    4999     .07       0
  5330.8      .1       0
Bank Sta=4995,4999
XS Rating Curve= 0 ,0
Exp/Cntr=0.3,0.1

Type RM Length L Ch R = 1 ,10360   ,366,366,366
BEGIN DESCRIPTION:
Mapping XS 5d681ec1
END DESCRIPTION:
XS GIS Cut Line= 2
      1866986.31     13913682.72      1867711.12     13913621.47
#Sta/Elev= 30
  4509.4 2118.42  4523.6 2117.03  4537.4 2115.67  4542.4 2115.73  4578.3 2113.15
  4618.5 2111.75  4638.6 2109.92    4657    2109    4662 2109.46  4668.7 2108.64
  4698.8 2107.27  4738.9 2106.27    4769 2104.54  4829.2 2103.43  4901.2 2101.36
  4929.6 2099.76  4979.8 2099.98  5013.8 2098.03  5014.1 2097.53  5017.6 2097.53
  5017.8 2098.03  5020.8 2098.78  5029.9 2098.21    5040 2098.73    5050 2100.36
    5060 2101.23  5110.2 2102.77  5140.4 2104.67  5190.5 2106.74  5236.8 2107.46
#Mann= 4 ,-1 , 0
  4509.4      .1       0  4523.6     .07       0  5013.8     .05       0
  5017.8     .07       0
Bank Sta=5013.8,5017.8
XS Rating Curve= 0 ,0
Exp/Cntr=0.3,0.1

Type RM Length L Ch R = 1 ,9994    ,219,219,219
BEGIN DESCRIPTION:
Stream0315 22.0
END DESCRIPTION:
XS GIS Cut Line= 3
      1867374.99       13913975.        1867475.       13913975.
      1867574.99       13913975.
#Sta/Elev= 28
  4899.9 2094.49  4902.4 2094.49  4909.9 2093.64  4919.9 2092.01  4929.9 2088.78
  4939.9 2084.19  4949.9 2079.18  4959.9 2075.35  4969.9 2071.39  4977.9 2066.64
  4978.2 2066.14  4981.7 2066.14  4981.9 2066.64  4989.9 2067.75  4997.4 2069.49
  4999.9 2069.49  5002.4 2069.49  5009.9  2071.4  5019.9 2075.16  5029.9 2079.19
  5039.9  2082.7  5049.9  2087.9  5059.9 2089.07  5069.9 2092.39  5079.9  2094.1
  5089.9 2094.76  5097.4 2095.03  5099.9 2095.03
#Mann= 3 ,-1 , 0
  4899.9     .07       0  4977.9     .05       0  4981.9     .07       0
Bank Sta=4977.9,4981.9
XS Rating Curve= 0 ,0
Exp/Cntr=0.3,0.1

Type RM Length L Ch R = 1 ,9775    ,246,246,246
BEGIN DESCRIPTION:
Mapping XS f95e9231
END DESCRIPTION:
XS GIS Cut Line= 2
      1867252.23     13914137.29      1867666.04     13914243.41
#Sta/Elev= 30
    4770 2098.54  4825.4 2095.59  4855.4 2094.48  4866.2 2093.38  4927.7 2089.57
  4942.6  2088.1  4948.4 2086.37    4969 2077.53  4978.2 2073.12  4983.3 2072.21
  4989.7 2067.41    5000 2063.72  5010.3 2062.48  5022.1 2062.03  5022.4 2061.53
  5025.9 2061.53  5026.1 2062.03  5030.9 2062.19  5041.3 2063.75  5051.6 2067.57
  5059.7  2069.4  5064.9 2070.13  5072.2 2072.33  5082.6 2074.18  5100.5 2079.29
  5113.5 2084.68  5134.2 2090.01  5141.3 2091.42  5175.5 2093.61  5197.2 2094.38
#Mann= 3 ,-1 , 0
    4770     .07       0  5022.1     .05       0  5026.1     .07       0
Bank Sta=5022.1,5026.1
XS Rating Curve= 0 ,0
Exp/Cntr=0.3,0.1

Type RM Length L Ch R = 1 ,9529    ,78,78,78
BEGIN DESCRIPTION:
Stream0315 21.0
END DESCRIPTION:
XS GIS Cut Line= 3
      1867275.03     13914325.02        1867425.       13914425.
      1867574.96       13914425.
#Sta/Elev= 30
  4815.1 2093.91  4818.1 2093.91  4828.6 2091.68  4837.6 2090.42  4843.6 2087.51
  4858.6 2083.67  4864.6 2081.26  4873.7 2079.11  4894.7 2073.34  4900.7 2072.24
  4909.7 2071.41  4915.7 2070.42  4945.8 2064.53  4959.3 2061.51  4972.8 2059.17
  4981.8 2058.49  4997.8 2058.34  5003.3  2057.9  5003.6  2057.4  5007.1  2057.4
  5007.3  2057.9  5015.3 2058.68  5035.3 2058.34  5045.3 2060.62  5065.3 2070.16
  5085.3 2076.75  5105.3  2084.6  5115.3  2087.1  5135.3 2089.26  5145.3 2089.15
#Mann= 3 ,-1 , 0
  4815.1     .07       0  5003.3     .05       0  5007.3     .07       0
Bank Sta=5003.3,5007.3
XS Rating Curve= 0 ,0
Exp/Cntr=0.3,0.1

Type RM Length L Ch R = 1 ,9451    ,96,96,96
BEGIN DESCRIPTION:
Mapping XS 390cd4b2
END DESCRIPTION:
XS GIS Cut Line= 4
       1867175.2     13914339.76      1867396.38     13914484.78
      1867455.16     13914519.76      1867561.34     13914532.29
#Sta/Elev= 30
  4702.2 2098.54  4777.6 2093.18  4798.7 2089.96  4807.8 2085.69  4813.8 2086.48
  4828.9 2077.93  4834.9 2080.78    4844 2077.69    4850 2079.42  4865.1 2072.48
  4871.1 2073.04  4880.2 2070.36  4886.2 2070.51  4901.3 2065.74  4916.4 2063.46
  4929.2 2060.11  4958.5 2057.96  4986.4 2054.69  4986.6 2054.19  4990.4 2054.69
  5010.9 2057.95  5023.3 2063.42  5032.1 2065.24  5038.6  2064.4  5055.1 2067.82
  5105.4 2074.28  5115.5 2076.71  5121.5 2079.94  5126.5 2079.65    5142 2084.31
#Mann= 3 ,-1 , 0
  4702.2     .07       0  4986.4     .05       0  4990.4     .07       0
Bank Sta=4986.4,4990.4
XS Rating Curve= 0 ,0
Exp/Cntr=0.3,0.1

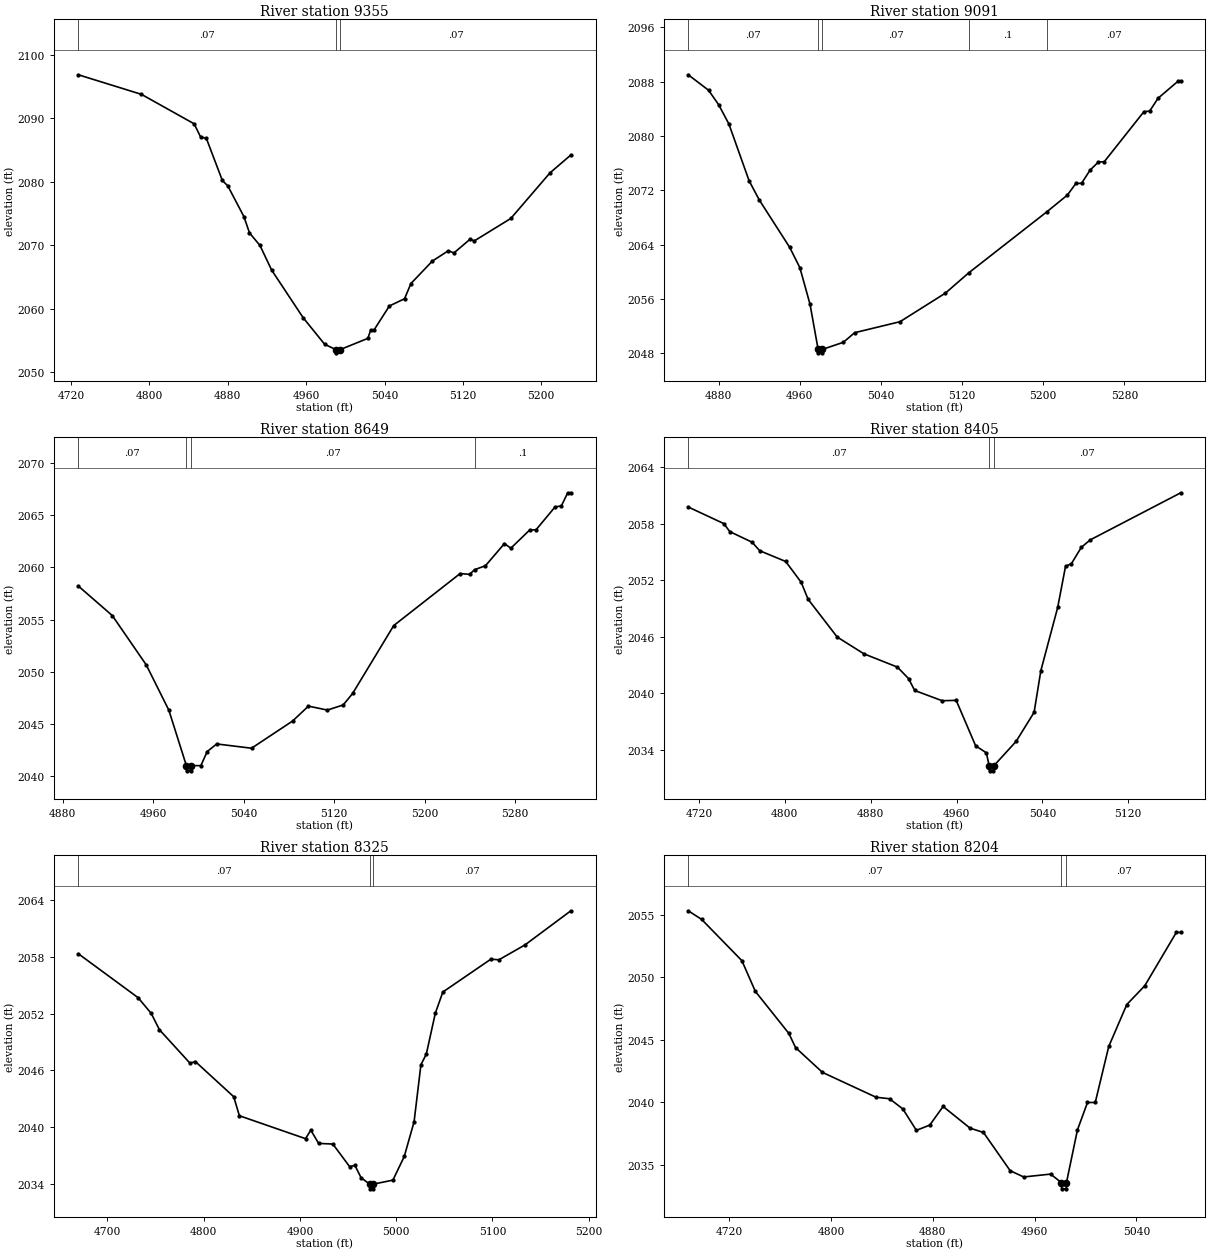
Type RM Length L Ch R = 1 ,9355    ,264,264,264
BEGIN DESCRIPTION:
Mapping XS e7b5b20f
END DESCRIPTION:
XS GIS Cut Line= 4
      1867130.39     13914451.35      1867394.98     13914590.54
      1867488.35     13914640.42      1867586.25     13914644.39
#Sta/Elev= 30
  4727.4  2096.9  4791.8 2093.81  4845.6 2089.16  4852.3 2087.05    4858 2086.89
  4874.4 2080.21    4880 2079.35  4896.4 2074.51  4902.1 2071.94  4912.8 2069.95
  4924.7 2066.07  4956.9 2058.54  4978.9 2054.34  4990.5  2053.5  4990.7    2053
  4994.5  2053.5    5023 2055.29  5025.8  2056.6  5029.2  2056.6  5044.9  2060.4
  5060.4 2061.54  5066.9 2063.94  5088.8 2067.49  5105.1 2069.12  5110.8 2068.77
    5127  2070.9  5131.8 2070.69  5168.9 2074.22  5208.9 2081.42  5230.2 2084.24
#Mann= 3 ,-1 , 0
  4727.4     .07       0  4990.5     .05       0  4994.5     .07       0
Bank Sta=4990.5,4994.5
XS Rating Curve= 0 ,0
Exp/Cntr=0.3,0.1

Type RM Length L Ch R = 1 ,9091    ,442,442,442
BEGIN DESCRIPTION:
Stream0315 20.0
END DESCRIPTION:
XS GIS Cut Line= 3
      1867175.01       13914825.        1867325.       13914825.
        1867625.       13914675.
#Sta/Elev= 30
  4850.1 2089.03  4870.1 2086.75  4880.1 2084.61  4890.1 2081.79  4910.1 2073.39
  4920.1 2070.57  4950.1 2063.58  4960.1 2060.59  4970.1  2055.2  4978.1 2048.54
  4978.3 2048.04  4981.8 2048.04  4982.1 2048.54  5002.9 2049.59  5014.1 2051.01
  5058.8 2052.63  5103.5 2056.84  5126.5 2059.83  5203.4 2068.82  5223.7 2071.29
  5232.1 2073.01  5237.7 2073.03  5246.1 2074.97  5254.4 2076.19    5260  2076.2
  5299.2  2083.6  5304.8 2083.67  5313.1 2085.57  5332.7 2088.07  5335.5 2088.07
#Mann= 5 ,-1 , 0
  4850.1     .07       0  4978.1     .05       0  4982.1     .07       0
  5126.5      .1       0  5203.4     .07       0
Bank Sta=4978.1,4982.1
XS Rating Curve= 0 ,0
Exp/Cntr=0.3,0.1

Type RM Length L Ch R = 1 ,8649    ,244,244,244
BEGIN DESCRIPTION:
Stream0315 19.0
END DESCRIPTION:
XS GIS Cut Line= 3
      1867375.05       13915225.        1867475.       13915225.
      1867625.02     13914924.97
#Sta/Elev= 30
    4894 2058.21    4924 2055.38    4954 2050.65    4974  2046.3  4989.5 2040.98
  4989.7 2040.48  4993.2 2040.48  4993.5 2040.98  5002.3 2040.98  5007.9 2042.33
  5016.3 2043.06  5047.1 2042.65  5083.4 2045.26  5097.4 2046.69  5114.1 2046.31
  5128.1  2046.8  5136.5 2047.91  5172.8 2054.42  5231.5 2059.41  5239.9 2059.33
  5244.2 2059.78  5253.9 2060.16  5270.7 2062.29  5276.3 2061.84    5293 2063.59
  5298.6 2063.61  5315.4  2065.8    5321  2065.9  5326.6 2067.16  5329.4 2067.16
#Mann= 4 ,-1 , 0
    4894     .07       0  4989.5     .05       0  4993.5     .07       0
  5244.2      .1       0
Bank Sta=4989.5,4993.5
XS Rating Curve= 0 ,0
Exp/Cntr=0.3,0.1

Type RM Length L Ch R = 1 ,8405    ,80,80,80
BEGIN DESCRIPTION:
Mapping XS 80527408
END DESCRIPTION:
XS GIS Cut Line= 3
      1867347.86     13915489.17      1867614.53     13915411.47
      1867779.31     13915336.01
#Sta/Elev= 30
    4710 2059.79  4743.1 2058.03  4748.7 2057.18  4769.5 2056.05  4776.6 2055.15
  4800.8 2054.01  4815.3 2051.79  4821.6 2050.01  4848.8 2045.99  4873.7 2044.21
  4904.9  2042.8  4915.3 2041.58    4921 2040.32  4946.6 2039.23  4959.7 2039.27
  4977.8 2034.45  4987.8  2033.7  4990.5 2032.29  4990.8 2031.79  4994.3 2031.79
  4994.5 2032.29  5015.5 2034.91  5032.3    2038  5038.6 2042.43  5054.3 2049.14
  5061.6  2053.5  5067.1 2053.78  5076.3 2055.51  5084.6  2056.3    5169  2061.3
#Mann= 3 ,-1 , 0
    4710     .07       0  4990.5     .05       0  4994.5     .07       0
Bank Sta=4990.5,4994.5
XS Rating Curve= 0 ,0
Exp/Cntr=0.3,0.1

Type RM Length L Ch R = 1 ,8325    ,121,121,121
BEGIN DESCRIPTION:
Mapping XS a2491f02
END DESCRIPTION:
XS GIS Cut Line= 3
      1867368.67     13915610.67       1867714.2     13915450.12
      1867826.18     13915382.74
#Sta/Elev= 30
  4669.8 2058.32  4731.9 2053.68  4745.5 2052.02    4754  2050.3  4785.8 2046.76
  4791.3 2046.94  4831.2 2043.22  4837.1 2041.21  4905.8 2038.79  4911.3 2039.69
  4919.4 2038.29  4934.2 2038.22  4951.6 2035.84  4957.1 2035.97  4963.5 2034.67
  4972.4 2033.99  4972.7 2033.49  4976.2 2033.49  4976.4 2033.99  4996.6 2034.41
  5008.4 2036.91  5018.6 2040.58  5025.7  2046.6  5031.3 2047.72  5040.7 2052.06
  5048.5 2054.28  5098.4 2057.75  5106.7 2057.68  5133.9 2059.26  5181.5 2062.86
#Mann= 3 ,-1 , 0
  4669.8     .07       0  4972.4     .05       0  4976.4     .07       0
Bank Sta=4972.4,4976.4
XS Rating Curve= 0 ,0
Exp/Cntr=0.3,0.1

Type RM Length L Ch R = 1 ,8204    ,430,430,430
BEGIN DESCRIPTION:
Stream0315 18.0
END DESCRIPTION:
XS GIS Cut Line= 3
      1867425.03     13915674.99        1867725.       13915575.
        1867775.       13915525.
#Sta/Elev= 30
  4687.9 2055.32  4698.4 2054.63    4730 2051.33  4740.6 2048.87  4766.9 2045.51
  4772.2 2044.37  4793.3 2042.39  4835.4  2040.4    4846 2040.28  4856.5 2039.46
  4867.1 2037.75  4877.6 2038.17  4888.1 2039.66  4909.2 2037.93  4919.8 2037.58
  4940.8 2034.52  4951.4 2034.02  4972.5 2034.25    4981 2033.57  4981.3 2033.07
  4984.8 2033.07    4985 2033.57  4993.6 2037.78  5001.5 2039.98  5007.6 2039.98
  5018.2 2044.46  5032.4 2047.82  5046.5 2049.32  5071.3 2053.59  5074.8 2053.59
#Mann= 3 ,-1 , 0
  4687.9     .07       0    4981     .05       0    4985     .07       0
Bank Sta=4981,4985
XS Rating Curve= 0 ,0
Exp/Cntr=0.3,0.1

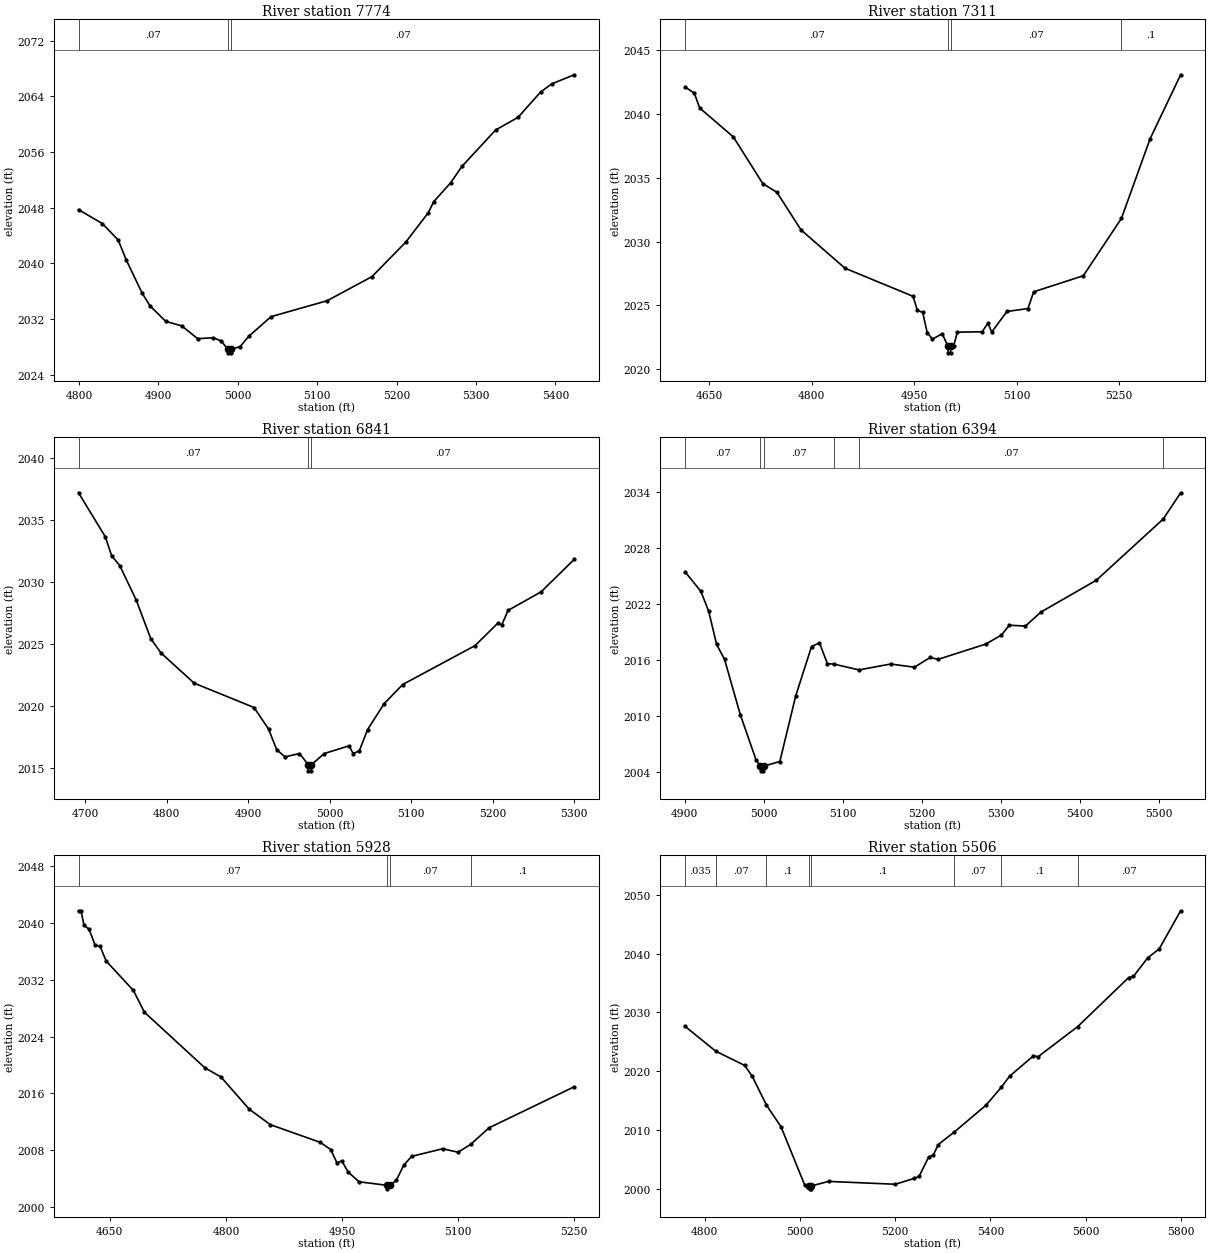
Type RM Length L Ch R = 1 ,7774    ,463,463,463
BEGIN DESCRIPTION:
Stream0315 17.0
END DESCRIPTION:
XS GIS Cut Line= 3
      1867624.96       13915975.        1867825.       13915975.
      1868124.99     13915675.01
#Sta/Elev= 30
  4799.4 2047.73  4829.4 2045.73  4849.4 2043.36  4859.4 2040.53  4879.4 2035.76
  4889.4 2033.91  4909.4 2031.66  4929.4 2031.03  4949.4 2029.19  4969.4 2029.32
  4979.4 2028.84  4987.4 2027.65  4987.7 2027.15  4991.2 2027.15  4991.4 2027.65
    5003 2028.05  5013.6  2029.5  5041.9 2032.35  5112.6 2034.64  5169.1 2038.11
  5211.6 2043.06  5239.9 2047.28  5246.9 2048.89  5268.1 2051.58  5282.3 2053.94
  5324.7 2059.17    5353 2060.99  5381.3 2064.62  5395.4  2065.8  5423.7 2067.11
#Mann= 3 ,-1 , 0
  4799.4     .07       0  4987.4     .05       0  4991.4     .07       0
Bank Sta=4987.4,4991.4
XS Rating Curve= 0 ,0
Exp/Cntr=0.3,0.1

Type RM Length L Ch R = 1 ,7311    ,470,470,470
BEGIN DESCRIPTION:
Stream0315 16.0
END DESCRIPTION:
XS GIS Cut Line= 3
      1867525.01     13916125.01        1867775.       13916425.
      1868074.99       13916575.
#Sta/Elev= 30
  4614.4 2042.11  4628.1 2041.62  4635.9 2040.46  4685.3 2038.19  4728.3 2034.54
  4749.1 2033.85  4784.3 2030.91  4848.7 2027.91  4948.3 2025.71  4954.8 2024.61
  4962.6 2024.44  4969.1 2022.86  4976.9 2022.36  4991.2 2022.78  4999.6 2021.78
  4999.9 2021.28  5003.4 2021.28  5003.6 2021.78  5007.7 2021.78  5013.3  2022.9
  5049.6 2022.93    5058  2023.6  5063.6 2022.91    5086 2024.52  5116.7 2024.75
  5125.1 2026.06  5197.8 2027.32  5253.6 2031.81  5295.6 2038.05  5340.3 2043.06
#Mann= 4 ,-1 , 0
  4614.4     .07       0  4999.6     .05       0  5003.6     .07       0
  5253.6      .1       0
Bank Sta=4999.6,5003.6
XS Rating Curve= 0 ,0
Exp/Cntr=0.3,0.1

Type RM Length L Ch R = 1 ,6841    ,447,447,447
BEGIN DESCRIPTION:
Stream0315 15.0
END DESCRIPTION:
XS GIS Cut Line= 3
      1867374.99       13916775.        1867675.       13916825.
      1867975.02       13916875.
#Sta/Elev= 30
  4691.7 2037.22  4724.7 2033.65  4732.3 2032.13  4742.4 2031.33  4762.7 2028.52
  4780.4 2025.42  4793.1 2024.26  4833.6 2021.83  4907.1 2019.86  4924.9 2018.12
    4935 2016.44  4945.2 2015.87  4962.9 2016.14  4973.6 2015.24  4973.8 2014.74
  4977.3 2014.74  4977.6 2015.24  4993.3 2016.14  5023.7 2016.76  5028.8 2016.13
  5036.4 2016.37  5046.5 2018.08  5066.8 2020.17  5089.6 2021.72  5178.3 2024.86
  5206.2 2026.67  5211.3 2026.56  5218.9 2027.71  5259.4 2029.21    5300 2031.83
#Mann= 3 ,-1 , 0
  4691.7     .07       0  4973.6     .05       0  4977.6     .07       0
Bank Sta=4973.6,4977.6
XS Rating Curve= 0 ,0
Exp/Cntr=0.3,0.1

Type RM Length L Ch R = 1 ,6394    ,466,466,466
BEGIN DESCRIPTION:
Stream0315 14.0
END DESCRIPTION:
XS GIS Cut Line= 3
      1867424.99       13917225.        1867525.       13917225.
      1868051.43     13917200.74
#Sta/Elev= 30
  4900.4 2025.49  4920.4 2023.41  4930.4 2021.26  4940.4 2017.71  4950.4 2016.12
  4970.4 2010.18  4990.4 2005.32  4995.9 2004.67  4996.2 2004.17  4999.7 2004.17
  4999.9 2004.67  5020.4 2005.17  5040.5  2012.2  5060.5 2017.48  5070.5 2017.88
  5080.5 2015.66  5089.4 2015.59  5120.5 2014.98  5160.6 2015.61  5190.6 2015.27
  5210.6 2016.31  5220.6 2016.11  5280.7 2017.74  5300.7 2018.71  5310.7 2019.77
    5331 2019.67  5350.8 2021.18  5420.9 2024.59  5505.5 2031.15  5527.4 2033.95
#Mann= 6 ,-1 , 0
  4900.4     .07       0  4995.9     .05       0  4999.9     .07       0
  5089.4      .1       0  5120.5     .07       0  5505.5      .1       0
Bank Sta=4995.9,4999.9
XS Rating Curve= 0 ,0
Exp/Cntr=0.3,0.1

Type RM Length L Ch R = 1 ,5928    ,422,422,422
BEGIN DESCRIPTION:
Stream0315 13.0
END DESCRIPTION:
XS GIS Cut Line= 3
      1867275.04     13917425.03        1867575.       13917675.
      1867825.04       13917675.
#Sta/Elev= 30
  4609.5 2041.71  4612.7 2041.71  4616.6 2039.67  4623.1 2039.12  4630.9 2036.89
  4637.4 2036.71  4645.2 2034.64  4680.4  2030.5  4694.7 2027.43  4772.8 2019.61
  4793.6 2018.32  4830.1 2013.79  4857.4 2011.61  4921.9 2009.12  4935.5  2008.1
  4943.3 2006.26  4949.8 2006.51  4957.7 2004.97    4972 2003.57    5008 2003.08
  5008.2 2002.58    5012 2003.08    5020 2003.76    5030 2005.94    5040 2007.15
    5080 2008.22    5100 2007.73  5116.4 2008.85    5140 2011.17    5250 2016.94
#Mann= 4 ,-1 , 0
  4609.5     .07       0    5008     .05       0    5012     .07       0
  5116.4      .1       0
Bank Sta=5008,5012
XS Rating Curve= 0 ,0
Exp/Cntr=0.3,0.1

Type RM Length L Ch R = 1 ,5506    ,484,484,484
BEGIN DESCRIPTION:
Stream0315 12.0
END DESCRIPTION:
XS GIS Cut Line= 3
      1867183.89     13918059.44      1867440.65     13918039.93
      1868224.26     13918061.24
#Sta/Elev= 30
  4758.4 2027.65  4822.8 2023.43  4883.9 2020.99  4899.9 2019.12  4929.5 2014.26
  4960.1 2010.58  5010.1 2000.64  5019.8 2000.52  5020.1 2000.02  5023.6 2000.02
  5023.8 2000.52  5060.3 2001.28  5200.3  2000.8  5240.3  2001.8  5250.3 2002.14
  5270.3 2005.41  5280.3 2005.77  5290.3 2007.52  5324.1 2009.67  5390.8 2014.23
  5422.7 2017.25  5440.4 2019.16  5490.4 2022.61  5500.4 2022.48  5583.7 2027.61
  5690.5 2035.92  5700.5 2036.11  5730.5 2039.27  5754.8  2040.8  5799.8 2047.28
#Mann= 8 ,-1 , 0
  4758.4    .035       0  4822.8     .07       0  4929.5      .1       0
  5019.8     .05       0  5023.8      .1       0  5324.1     .07       0
  5422.7      .1       0  5583.7     .07       0
Bank Sta=5019.8,5023.8
XS Rating Curve= 0 ,0
Exp/Cntr=0.3,0.1

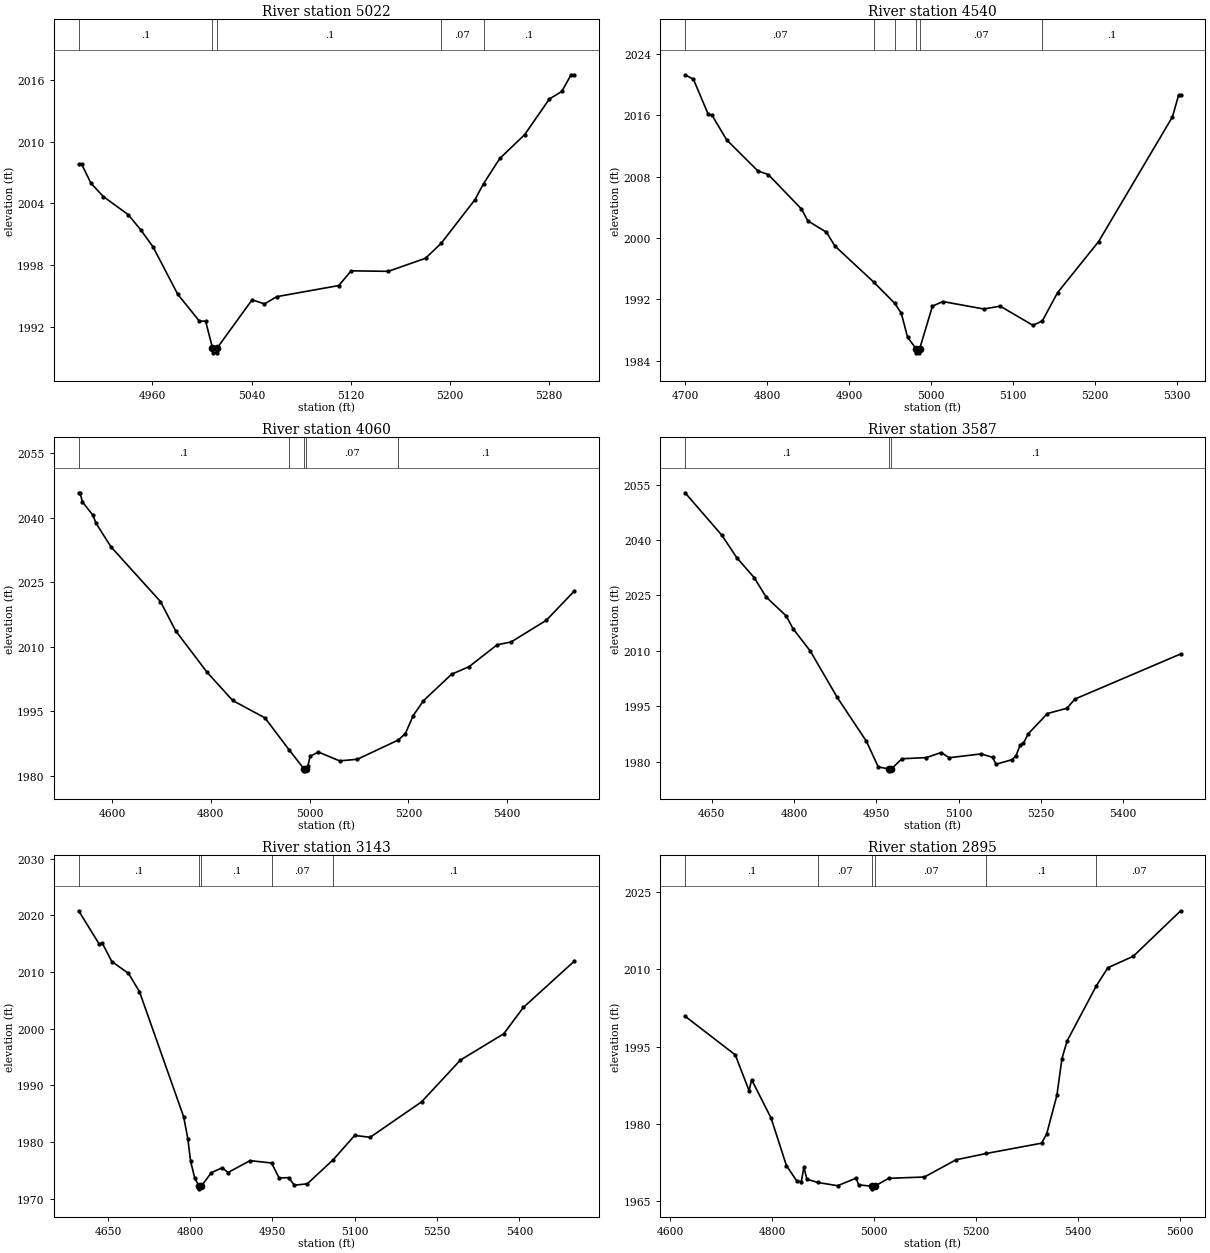
Type RM Length L Ch R = 1 ,5022    ,482,482,482
BEGIN DESCRIPTION:
Stream0315 11.0
END DESCRIPTION:
XS GIS Cut Line= 3
        1867375.       13918475.        1867475.       13918475.
        1867775.       13918475.
#Sta/Elev= 30
  4900.4 2007.78  4902.9 2007.78  4910.4 2005.94  4920.4 2004.65  4940.4  2002.9
  4950.4 2001.44  4960.4 1999.78  4980.4 1995.16  4997.9 1992.55  5002.9 1992.55
  5008.4 1989.97  5008.7 1989.47  5012.2 1989.47  5012.4 1989.97  5040.4 1994.62
  5050.4 1994.23  5060.4 1994.93  5110.4 1996.01  5120.4 1997.44  5150.4 1997.39
  5180.4 1998.66  5193.1 2000.12  5220.4 2004.37  5227.3 2005.92  5240.4 2008.36
  5260.4 2010.67  5280.4 2014.14  5290.4 2014.87  5297.9 2016.49  5300.4 2016.49
#Mann= 5 ,-1 , 0
  4900.4      .1       0  5008.4     .05       0  5012.4      .1       0
  5193.1     .07       0  5227.3      .1       0
Bank Sta=5008.4,5012.4
XS Rating Curve= 0 ,0
Exp/Cntr=0.3,0.1

Type RM Length L Ch R = 1 ,4540    ,480,480,480
BEGIN DESCRIPTION:
Stream0315 10.0
END DESCRIPTION:
XS GIS Cut Line= 3
      1867174.98       13918875.        1867475.       13918925.
      1867775.04       13918925.
#Sta/Elev= 30
  4700.2 2021.26  4710.4 2020.67  4728.1 2016.18  4733.2 2015.96  4750.9 2012.78
  4788.9 2008.74  4801.6 2008.27  4842.1 2003.78  4849.8 2002.24  4872.6 2000.75
  4882.7 1998.98  4930.3 1994.25  4955.6 1991.52  4963.8 1990.22  4971.4 1987.09
  4982.1 1985.55  4982.3 1985.05  4985.8 1985.05  4986.1 1985.55  5001.8 1991.13
  5014.4 1991.73  5064.4 1990.76  5084.4 1991.13  5124.4 1988.63  5135.8 1989.21
  5154.4  1992.9  5204.4 1999.54  5294.4 2015.78  5301.9  2018.6  5304.4  2018.6
#Mann= 6 ,-1 , 0
  4700.2     .07       0  4930.3      .1       0  4955.6     .07       0
  4982.1     .05       0  4986.1     .07       0  5135.8      .1       0
Bank Sta=4982.1,4986.1
XS Rating Curve= 0 ,0
Exp/Cntr=0.3,0.1

Type RM Length L Ch R = 1 ,4060    ,473,473,473
BEGIN DESCRIPTION:
Stream0315 9.0
END DESCRIPTION:
XS GIS Cut Line= 3
      1866975.01     13919125.01        1867375.       13919375.
        1867725.       13919775.
#Sta/Elev= 30
  4532.3 2045.77  4535.2 2045.77    4540 2043.64  4561.2 2040.56  4567.7 2038.64
  4597.7 2033.21    4698 2020.47  4728.6 2013.69  4792.3 2004.03  4844.2 1997.46
  4909.6 1993.41    4959 1985.89  4988.2  1981.6  4988.5  1981.1  4992.6  1981.6
  4996.3 1982.21    5001 1984.49  5017.8 1985.47  5060.5 1983.42  5096.5 1983.79
  5179.5 1988.27  5193.8 1989.76  5209.5 1993.93  5230.4 1997.41  5287.3 2003.56
  5322.9 2005.34  5379.4 2010.41  5407.8 2011.07    5479  2016.1  5535.5 2022.88
#Mann= 5 ,-1 , 0
  4532.3      .1       0    4959     .07       0  4988.2     .05       0
  4992.6     .07       0  5179.5      .1       0
Bank Sta=4988.2,4992.6
XS Rating Curve= 0 ,0
Exp/Cntr=0.3,0.1

Type RM Length L Ch R = 1 ,3587    ,444,444,444
BEGIN DESCRIPTION:
Stream0315 8.0
END DESCRIPTION:
XS GIS Cut Line= 3
      1866824.98     13919274.97        1867025.       13919625.
      1867424.96     13919924.97
#Sta/Elev= 30
  4601.5 2052.79  4668.5 2041.29  4695.8 2035.19  4727.5  2029.8  4749.1 2024.57
  4785.8 2019.43    4798 2016.03  4829.7 2009.92  4878.7 1997.39  4931.9  1985.5
  4953.5 1978.57  4972.9 1977.99  4973.2 1977.49  4977.3 1977.99  4996.7 1980.76
  5041.1 1981.08  5068.2 1982.45  5082.8 1981.04  5141.1 1982.08  5161.9 1981.14
  5168.2 1979.28  5197.4 1980.51  5204.6 1981.58  5211.9 1984.41  5218.2 1984.94
  5226.5 1987.47  5261.9 1993.01  5297.4 1994.44  5311.9 1996.93  5504.6 2009.14
#Mann= 3 ,-1 , 0
  4601.5      .1       0  4972.9     .05       0  4977.3      .1       0
Bank Sta=4972.9,4977.3
XS Rating Curve= 0 ,0
Exp/Cntr=0.3,0.1

Type RM Length L Ch R = 1 ,3143    ,248,248,248
BEGIN DESCRIPTION:
Stream0315 7.0
END DESCRIPTION:
XS GIS Cut Line= 3
      1866675.01     13919525.05        1866725.       13919925.
      1867025.02     13920325.03
#Sta/Elev= 30
  4596.7 2020.81  4634.4  2014.9  4639.5 2015.16  4657.1 2011.86  4687.4 2009.78
  4707.5 2006.56  4788.1 1984.46  4795.7 1980.59  4800.7 1976.65  4808.3 1973.64
  4816.1 1972.25  4816.5 1971.75  4820.6 1972.25  4838.5 1974.61  4858.7 1975.48
  4868.8 1974.62  4909.1 1976.73  4948.3 1976.31    4962 1973.68  4979.6 1973.72
  4989.7  1972.4  5013.3 1972.63  5060.7 1976.89  5099.8 1981.18  5127.9 1980.84
  5221.6 1987.09  5292.5 1994.47  5371.6 1999.12  5407.1 2003.75  5499.8  2011.9
#Mann= 5 ,-1 , 0
  4596.7      .1       0  4816.1     .05       0  4820.6      .1       0
  4948.3     .07       0  5060.7      .1       0
Bank Sta=4816.1,4820.6
XS Rating Curve= 0 ,0
Exp/Cntr=0.3,0.1

Type RM Length L Ch R = 1 ,2895    ,615,615,615
BEGIN DESCRIPTION:
Stream0315 6.0
END DESCRIPTION:
XS GIS Cut Line= 3
       1866572.2       13919707.      1866535.59     13920088.23
      1866553.41     13920677.88
#Sta/Elev= 30
    4629  2000.9  4727.5 1993.38  4754.6  1986.4  4759.6 1988.55  4797.8 1981.08
  4827.9 1971.84    4848 1968.86  4857.2  1968.7  4862.2 1971.52  4868.1 1969.18
    4889 1968.55  4928.4 1967.91  4964.7 1969.38  4969.7 1968.08  4996.4  1967.8
  4996.7  1967.3  5000.9  1967.8  5028.8 1969.35  5098.8  1969.6  5160.8 1972.95
  5220.7 1974.19  5328.9 1976.19  5338.9 1977.98  5358.9 1985.48  5368.9 1992.64
  5378.9 1996.08  5436.2 2006.78    5459 2010.34    5509 2012.58  5601.9 2021.43
#Mann= 6 ,-1 , 0
    4629      .1       0    4889     .07       0  4996.4     .05       0
  5000.9     .07       0  5220.7      .1       0  5436.2     .07       0
Bank Sta=4996.4,5000.9
XS Rating Curve= 0 ,0
Exp/Cntr=0.3,0.1

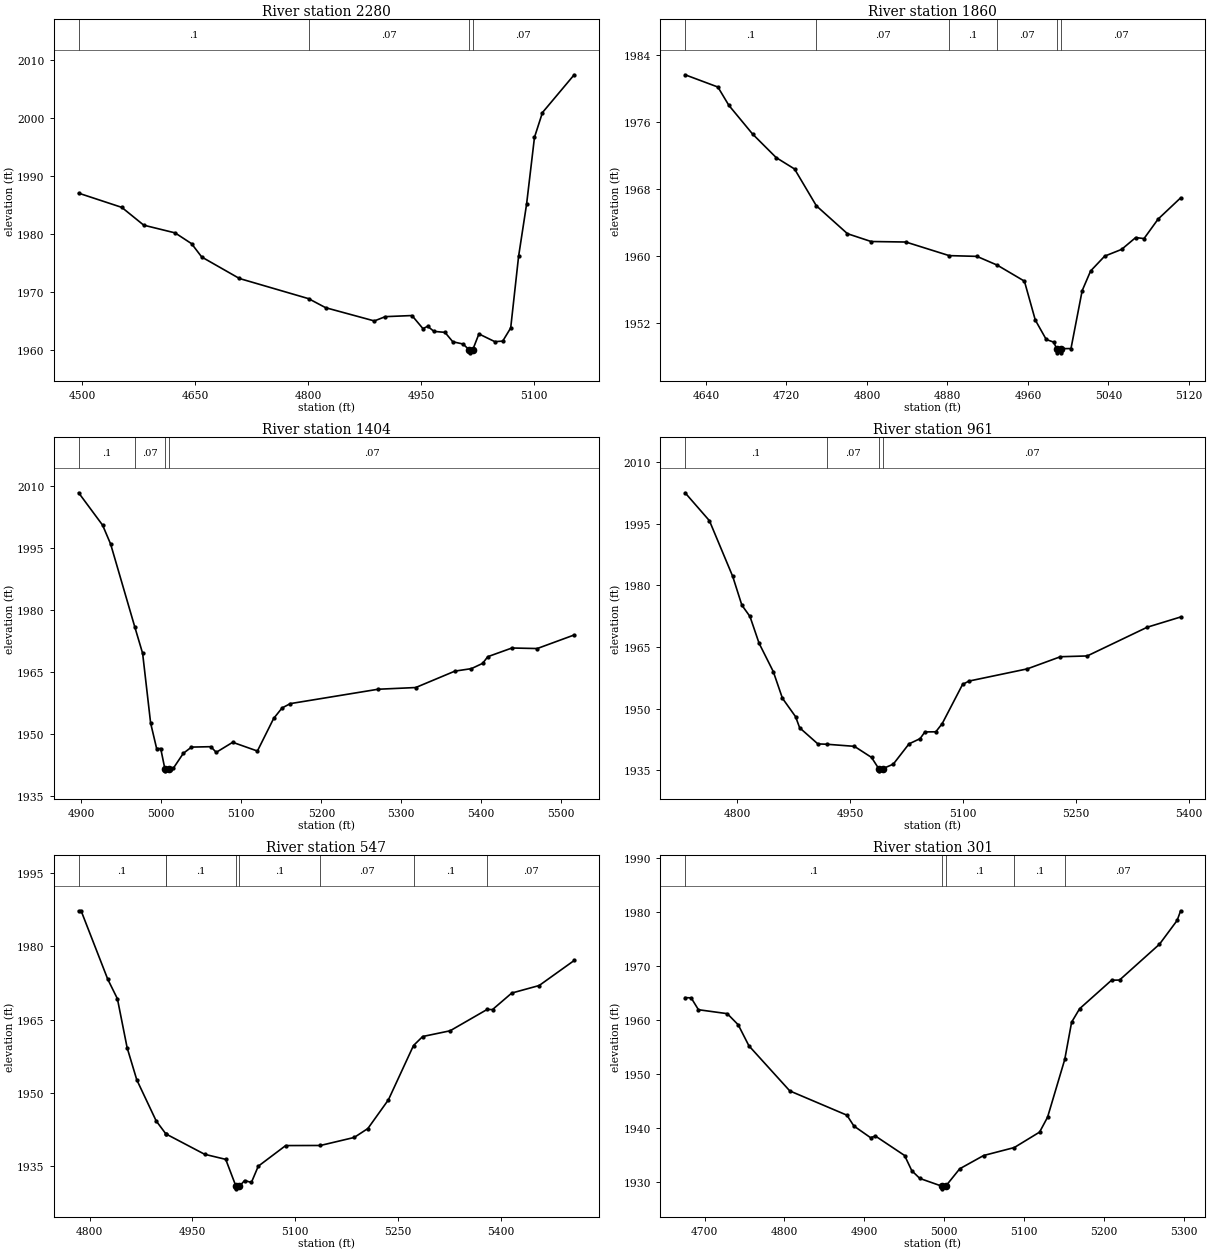
Type RM Length L Ch R = 1 ,2280    ,420,420,420
BEGIN DESCRIPTION:
Stream0315 5.0
END DESCRIPTION:
XS GIS Cut Line= 3
        1866425.       13919875.        1866125.       13920275.
        1866075.     13920424.99
#Sta/Elev= 30
  4495.4 1987.05  4552.7  1984.6  4581.9 1981.53  4623.5  1980.2  4645.4 1978.34
  4658.9 1976.04  4708.9 1972.34  4800.8 1968.86  4823.5  1967.3  4888.1 1965.02
  4902.7 1965.76  4938.1 1965.95  4952.7 1963.69  4958.9  1964.1  4967.3 1963.22
  4981.9 1963.05  4992.3 1961.43  5005.9 1961.04  5014.2 1960.02  5014.5 1959.52
  5018.7 1960.02    5027 1962.78  5048.1 1961.45  5058.6 1961.54  5069.2 1963.81
  5079.7 1976.17  5090.3 1985.15  5100.8 1996.69  5111.4 2000.95  5153.5 2007.46
#Mann= 4 ,-1 , 0
  4495.4      .1       0  4800.8     .07       0  5014.2     .05       0
  5018.7     .07       0
Bank Sta=5014.2,5018.7
XS Rating Curve= 0 ,0
Exp/Cntr=0.3,0.1

Type RM Length L Ch R = 1 ,1860    ,456,456,456
BEGIN DESCRIPTION:
Stream0315 4.0
END DESCRIPTION:
XS GIS Cut Line= 3
      1866224.98     13919825.01        1865875.       13919975.
      1865824.99     13920075.02
#Sta/Elev= 30
  4619.2 1981.62  4651.8 1980.16  4662.7 1977.98  4686.3 1974.56  4709.8 1971.75
    4728  1970.4  4749.7 1966.01  4780.6 1962.69  4804.1 1961.76  4838.6  1961.7
  4881.7 1960.08  4909.3 1959.99  4929.6 1958.94  4956.5 1957.04  4967.3 1952.41
  4978.2 1950.09  4985.5 1949.78  4988.6    1949    4989  1948.5  4992.9  1948.5
  4993.2    1949  5002.8 1949.01  5013.9  1955.9  5022.3 1958.25  5036.3 1960.02
  5053.1 1960.82  5067.1 1962.23  5075.4 1962.11  5089.4 1964.43  5111.8 1966.96
#Mann= 6 ,-1 , 0
  4619.2      .1       0  4749.7     .07       0  4881.7      .1       0
  4929.6     .07       0  4988.6     .05       0  4993.2     .07       0
Bank Sta=4988.6,4993.2
XS Rating Curve= 0 ,0
Exp/Cntr=0.3,0.1

Type RM Length L Ch R = 1 ,1404    ,443,443,443
BEGIN DESCRIPTION:
Stream0315 3.0
END DESCRIPTION:
XS GIS Cut Line= 3
        1865625.     13919575.01        1865625.       13919675.
      1865747.25     13920179.92
#Sta/Elev= 30
  4896.6 2008.38  4926.6 2000.54  4936.6 1995.98  4966.7 1976.01  4976.6 1969.56
  4986.6 1952.71  4994.1 1946.55  4999.2 1946.55  5004.4 1941.65  5004.8 1941.15
  5009.3 1941.65  5014.9 1941.75  5027.5 1945.39  5037.7 1946.89  5061.9 1946.99
  5068.6 1945.62  5089.2 1948.05  5120.1 1945.94  5140.4 1953.81  5150.9 1956.35
  5161.2  1957.4    5271 1960.88    5318 1961.29    5367 1965.26  5387.6 1965.86
  5401.7 1967.14  5408.1 1968.75  5438.3 1970.85  5469.9 1970.72  5516.1    1974
#Mann= 4 ,-1 , 0
  4896.6      .1       0  4966.7     .07       0  5004.4     .05       0
  5009.3     .07       0
Bank Sta=5004.4,5009.3
XS Rating Curve= 0 ,0
Exp/Cntr=0.3,0.1

Type RM Length L Ch R = 1 ,961     ,414,414,414
BEGIN DESCRIPTION:
Stream0315 2.0
END DESCRIPTION:
XS GIS Cut Line= 3
      1865074.97     13919874.99        1865325.       13919975.
      1865640.44     13920202.83
#Sta/Elev= 30
  4730.7 2002.58    4763 1995.78    4794 1982.19  4806.1 1975.21  4816.9 1972.44
    4829 1965.92  4847.9 1959.01    4860 1952.53  4877.5 1948.03  4882.9 1945.33
  4907.1  1941.4  4918.9 1941.32  4955.6 1940.81  4978.4 1938.11  4988.1 1935.34
  4988.5 1934.84    4993 1935.34  5007.3 1936.47  5028.2 1941.41  5042.9 1942.68
  5049.3 1944.32  5063.8 1944.35  5072.3 1946.34  5099.4  1955.9  5107.9 1956.71
  5185.3 1959.68  5229.4 1962.64    5265 1962.83  5344.7 1969.83  5389.1 1972.32
#Mann= 4 ,-1 , 0
  4730.7      .1       0  4918.9     .07       0  4988.1     .05       0
    4993     .07       0
Bank Sta=4988.1,4993
XS Rating Curve= 0 ,0
Exp/Cntr=0.3,0.1

Type RM Length L Ch R = 1 ,547     ,246,246,246
BEGIN DESCRIPTION:
Stream0315 1.0
END DESCRIPTION:
XS GIS Cut Line= 3
      1865024.97     13920124.97        1865175.       13920275.
      1865686.08     13920268.43
#Sta/Elev= 30
  4783.9 1987.27  4787.5 1987.27  4826.4 1973.27  4840.5 1969.27  4854.7 1959.25
  4868.8 1952.68  4897.1 1944.28  4911.1 1941.66  4911.9 1941.58  4967.8 1937.46
  4998.6 1936.42  5013.6 1930.89    5014 1930.39  5018.5 1930.89  5026.1 1932.09
  5036.1  1931.7  5046.1 1935.02  5086.1 1939.24  5136.8 1939.26  5186.1  1940.9
  5206.1 1942.73  5236.1 1948.61  5272.7 1959.71  5286.1 1961.55  5326.1 1962.72
  5380.2 1967.09    5388 1967.06  5416.1 1970.44  5456.1 1971.98  5507.2  1977.1
#Mann= 8 ,-1 , 0
  4783.9      .1       0  4911.1     .07       0  4911.9      .1       0
  5013.6     .05       0  5018.5      .1       0  5136.8     .07       0
  5272.7      .1       0  5380.2     .07       0
Bank Sta=5013.6,5018.5
XS Rating Curve= 0 ,0
Exp/Cntr=0.3,0.1

Type RM Length L Ch R = 1 ,301     ,224,224,224
BEGIN DESCRIPTION:
Stream0315 0.0
END DESCRIPTION:
XS GIS Cut Line= 4
      1865098.57     13920259.49       1865197.5     13920409.53
      1865272.01     13920461.93      1865621.51     13920470.17
#Sta/Elev= 30
  4675.7 1964.19  4683.3 1964.14  4692.4 1961.95  4728.5 1961.22  4742.2 1959.16
  4755.6 1955.27  4806.8 1946.92  4878.3 1942.43    4887 1940.43  4907.9 1938.27
    4914 1938.57  4950.5 1934.97  4959.5 1932.16  4969.5 1930.73    4997  1929.3
  4997.4  1928.8    5002  1929.3  5019.5 1932.51  5049.5 1934.97  5087.8 1936.44
  5119.5  1939.3  5129.5 1942.06    5151 1952.74  5159.6 1959.64  5169.6 1962.13
  5209.6 1967.41  5219.6 1967.44  5269.6 1974.07  5291.7 1978.47  5296.1 1980.26
#Mann= 5 ,-1 , 0
  4675.7      .1       0    4997     .05       0    5002      .1       0
  5087.8      .1       0    5151     .07       0
Bank Sta=4997,5002
XS Rating Curve= 0 ,0
Exp/Cntr=0.3,0.1

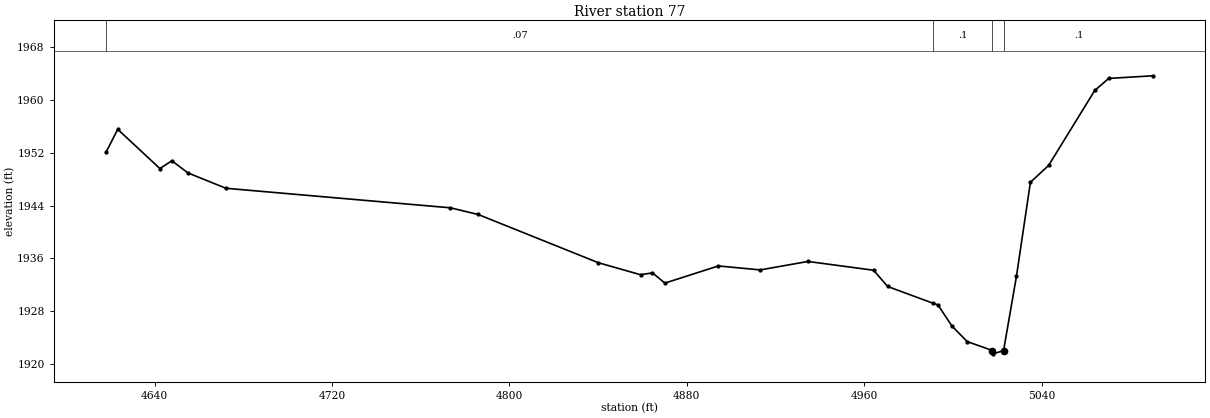
Type RM Length L Ch R = 1 ,77      ,0,0,0
BEGIN DESCRIPTION:
Stream0315 0.1
END DESCRIPTION:
XS GIS Cut Line= 3
      1865119.87     13920330.64      1865242.49     13920642.08
      1865351.55     13920725.47
#Sta/Elev= 30
  4618.2 1952.15  4623.4 1955.58  4642.4 1949.63  4647.8 1950.81  4655.1 1948.96
  4672.2 1946.64  4773.4 1943.68  4785.9 1942.67  4840.1 1935.36  4859.1 1933.54
  4864.5 1933.82  4870.1 1932.27  4894.2 1934.87  4913.1 1934.27  4934.6 1935.55
  4964.2 1934.22  4970.5 1931.76  4990.9 1929.23  4993.2 1928.97  4999.5 1925.77
  5006.4 1923.41  5017.8 1922.05  5018.2 1921.55  5022.8 1922.05  5028.6  1933.3
  5034.9 1947.55  5043.1  1950.1  5063.9 1961.46  5070.2 1963.29  5090.2 1963.69
#Mann= 4 ,-1 , 0
  4618.2     .07       0  4990.9      .1       0  5017.8     .05       0
  5022.8      .1       0
Bank Sta=5017.8,5022.8
XS Rating Curve= 0 ,0
Exp/Cntr=0.3,0.1

Chan Stop Cuts=-1
Use User Specified Reach Order=0
Composite Channel Slope=5