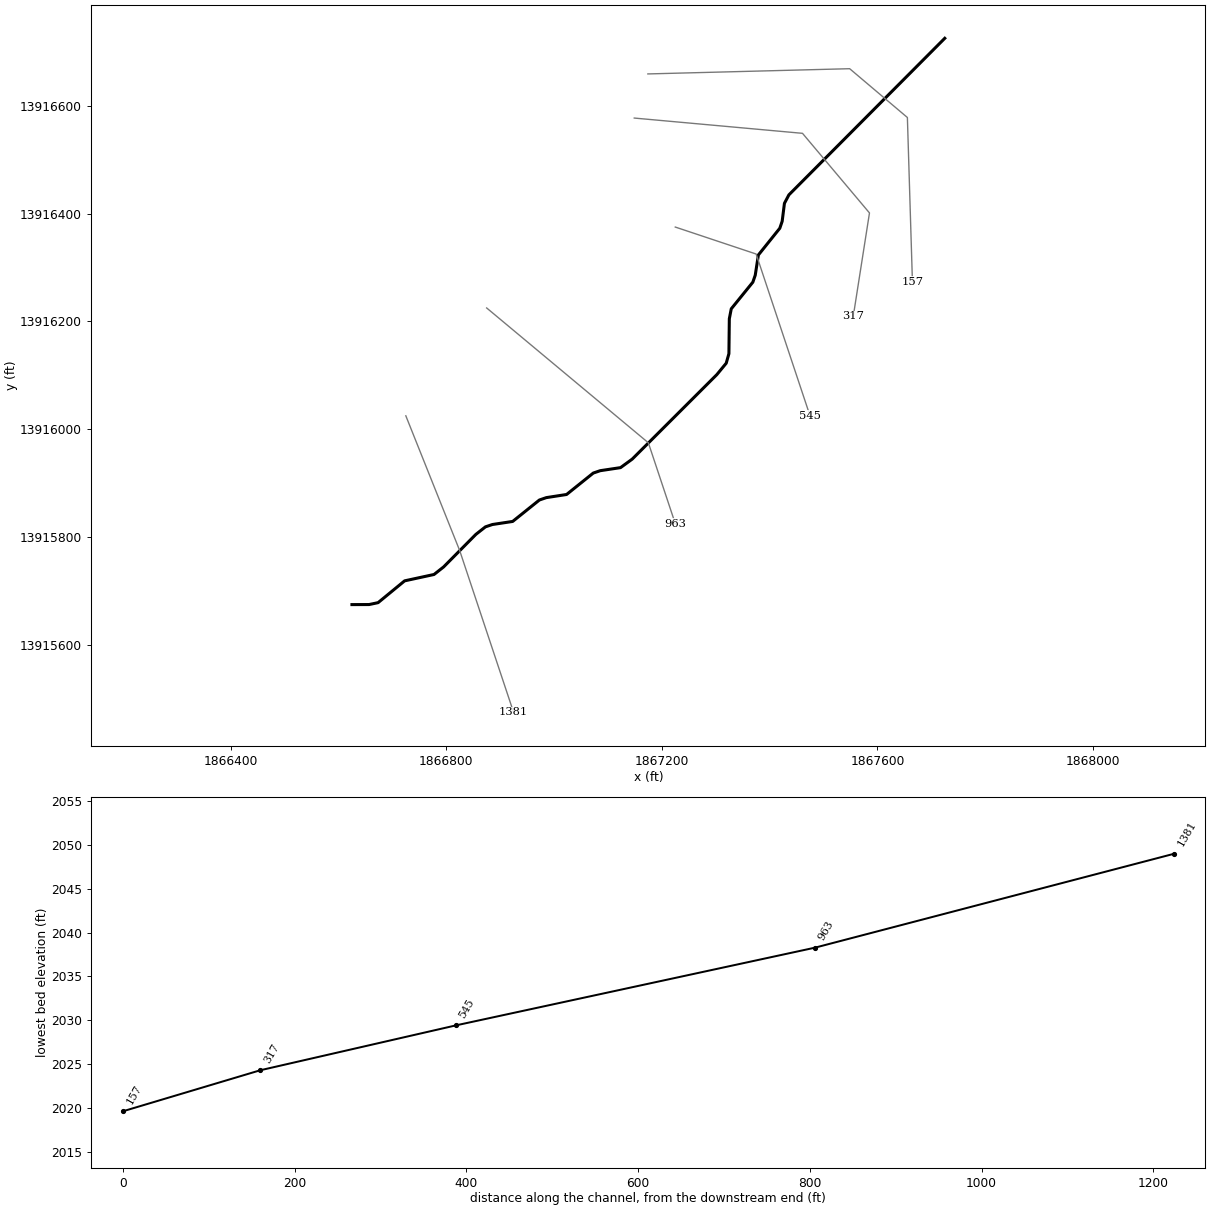
--- Stream0316.prj (project) ---

Proj Title=Stream0316 Base Level Engineering
Current Plan=p01
Default Exp/Contr=0.3,0.1
English Units
Geom File=g01
Flow File=f01
Plan File=p01
BEGIN DESCRIPTION:
Stream0316
END DESCRIPTION:

--- Stream0316.p01 (plan) ---

Plan Title=Multiple Run
Short Identifier=Multiple
Geom File=g01
Flow File=f01
Subcritical Flow
K Sum by GR= 0
Std Step Tol= 0.01
Critical Tol= 0.01
Num of Std Step Trials= 20
Max Error Tol= 0.3
Flow Tol Ratio= 0.001
Split Flow NTrial= 30
Split Flow Tol= 0.02
Split Flow Ratio= 0.02
Log Output Level= 0
Friction Slope Method= 1
Unsteady Friction Slope Method= 2
Unsteady Bridges Friction Slope Method= 1
Parabolic Critical Depth
Global Vel Dist=  1 , 1 , 1
Global Log Level= 0
CheckData=True
Encroach Param= -1, 0, 0, 0
BEGIN DESCRIPTION:
Multiple Run
END DESCRIPTION:

--- Stream0316.f01 (steady flow) ---

Flow Title=Multiple
Number of Profiles=7
Profile Names=10-year,25-year,50-year,1pct_min,100-year,1pct_plu,500-year
River Rch & RM= Stream0316,Reach-1,1381
     370     589     785     508    1014    2023    1665
Boundary for River Rch & Prof#=Stream0316,Reach-1,1
Up Type=0
Dn Type=3
Dn Slope=0.005
Boundary for River Rch & Prof#=Stream0316,Reach-1,2
Up Type=0
Dn Type=3
Dn Slope=0.005
Boundary for River Rch & Prof#=Stream0316,Reach-1,3
Up Type=0
Dn Type=3
Dn Slope=0.005
Boundary for River Rch & Prof#=Stream0316,Reach-1,4
Up Type=0
Dn Type=3
Dn Slope=0.005
Boundary for River Rch & Prof#=Stream0316,Reach-1,5
Up Type=0
Dn Type=3
Dn Slope=0.005
Boundary for River Rch & Prof#=Stream0316,Reach-1,6
Up Type=0
Dn Type=3
Dn Slope=0.005
Boundary for River Rch & Prof#=Stream0316,Reach-1,7
Up Type=0
Dn Type=3
Dn Slope=0.005

--- Stream0316.g01 (geometry) ---

Geom Title=Existing Conditions

River Reach=Stream0316,Reach-1
Reach XY= 30
      1866625.00     13915675.00      1866656.81     13915675.10
      1866673.51     13915678.60      1866722.76     13915719.03
      1866777.30     13915730.83      1866795.07     13915744.82
      1866854.93     13915805.18      1866872.71     13915819.15
      1866885.63     13915823.49      1866923.26     13915829.19
      1866972.80     13915868.92      1866985.69     13915873.35
      1867023.28     13915879.16      1867072.81     13915918.90
      1867085.70     13915923.30      1867123.37     13915928.95
      1867145.09     13915944.78      1867302.12     13916101.48
      1867319.48     13916122.57      1867324.48     13916140.22
      1867325.24     13916204.90      1867328.83     13916223.41
      1867368.88     13916272.82      1867373.33     13916285.69
      1867379.16     13916323.28      1867418.90     13916372.81
      1867423.30     13916385.70      1867427.50     13916418.97
      1867435.76     13916434.68      1867725.00     13916725.00

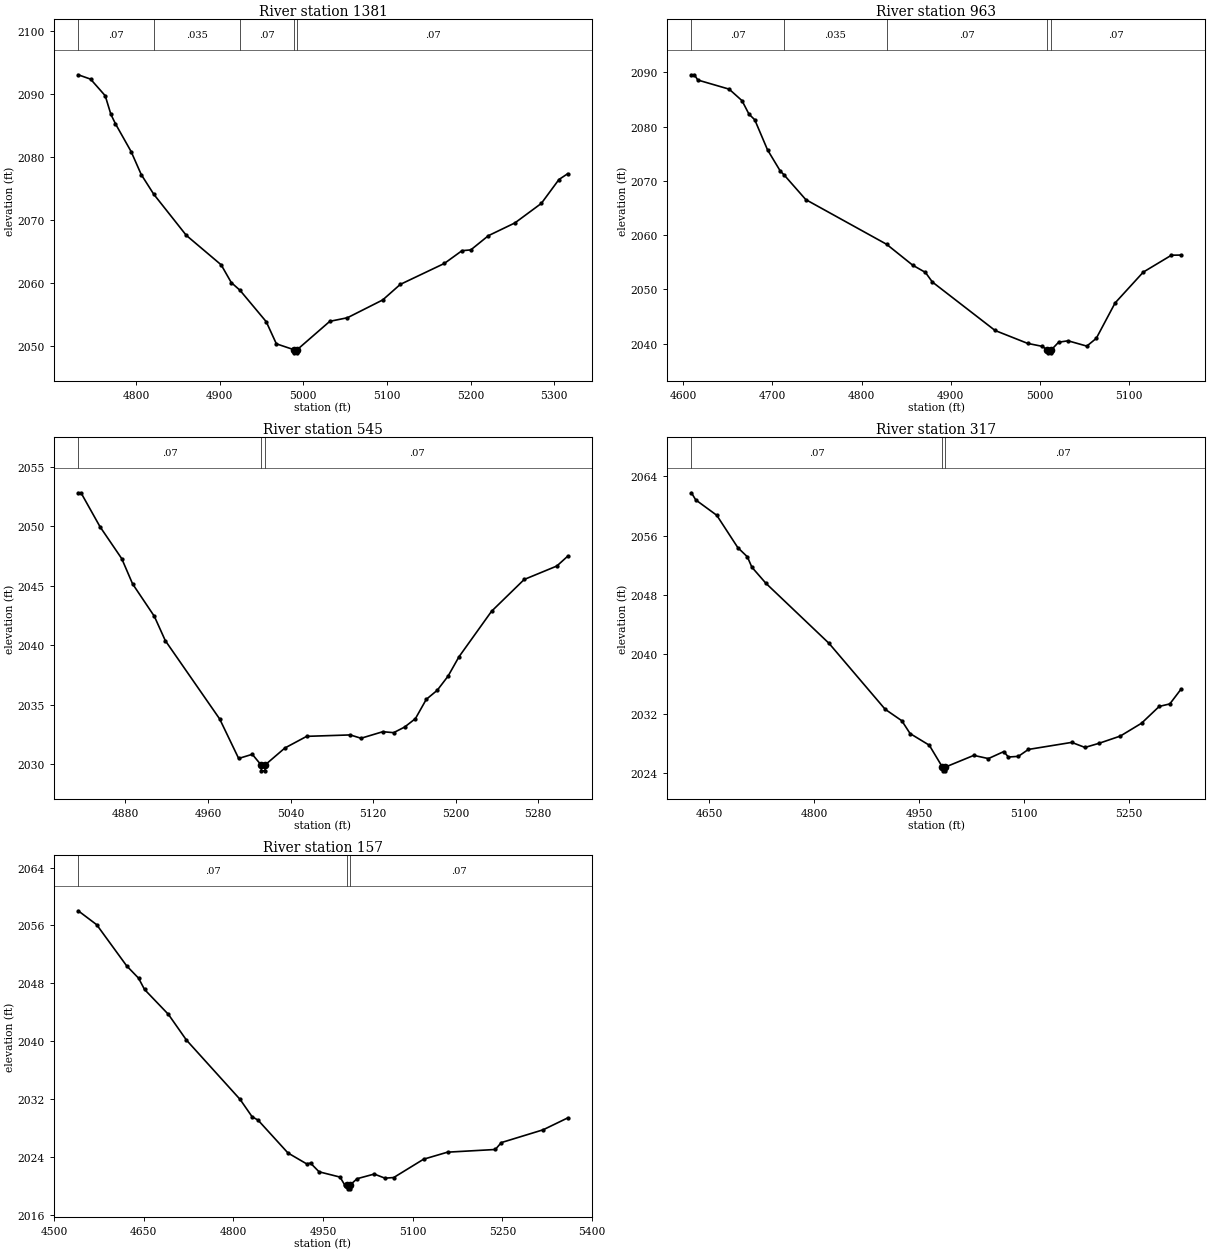
Type RM Length L Ch R = 1,1381,418,418,418
BEGIN DESCRIPTION:
Stream0316 3.0
END DESCRIPTION:
XS GIS Cut Line= 3
      1866724.99     13916025.02      1866825.00     13915775.00
      1866925.00     13915475.01
#Sta/Elev= 30
  4730.7 2093.01  4745.5 2092.32  4763.0 2089.69  4769.8 2086.74  4775.2 2085.26
  4794.0 2080.84  4806.1 2077.20  4821.1 2074.08  4860.0 2067.57  4901.7 2062.90
  4913.8 2060.09  4924.2 2058.87  4955.6 2053.89  4967.7 2050.39  4988.6 2049.46
  4988.8 2048.96  4992.3 2048.96  4992.6 2049.46  5031.6 2053.95  5052.7 2054.52
  5094.9 2057.34  5115.9 2059.80  5168.6 2063.12  5189.7 2065.14  5200.3 2065.27
  5221.3 2067.52  5253.0 2069.54  5284.6 2072.63  5305.7 2076.42  5316.2 2077.34
#Mann=5,-1,0
  4730.7    0.07       0  4821.1   0.035       0  4924.2    0.07       0
  4988.6    0.05       0  4992.6    0.07       0
Bank Sta=4988.6,4992.6
Exp/Cntr=0.3,0.1

Type RM Length L Ch R = 1,963,418,418,418
BEGIN DESCRIPTION:
Stream0316 2.0
END DESCRIPTION:
XS GIS Cut Line= 3
      1866874.98     13916225.02      1867175.00     13915975.00
      1867225.01     13915824.96
#Sta/Elev= 30
  4609.2 2089.56  4612.5 2089.56  4616.4 2088.59  4651.5 2086.91  4665.9 2084.79
  4673.7 2082.31  4680.2 2081.26  4694.5 2075.72  4708.8 2071.81  4713.0 2071.11
  4737.4 2066.54  4828.0 2058.30  4857.2 2054.45  4871.5 2053.11  4879.3 2051.34
  4949.6 2042.40  4986.1 2040.02  5002.4 2039.48  5008.3 2038.78  5008.5 2038.28
  5012.0 2038.28  5012.3 2038.78  5020.8 2040.24  5031.4 2040.50  5052.4 2039.52
  5063.0 2040.95  5084.1 2047.48  5115.7 2053.17  5147.3 2056.29  5157.9 2056.31
#Mann=5,-1,0
  4609.2    0.07       0  4713.0   0.035       0  4828.0    0.07       0
  5008.3    0.05       0  5012.3    0.07       0
Bank Sta=5008.3,5012.3
Exp/Cntr=0.3,0.1

Type RM Length L Ch R = 1,545,228,228,228
BEGIN DESCRIPTION:
Stream0316 1.0
END DESCRIPTION:
XS GIS Cut Line= 3
      1867224.96     13916375.01      1867375.00     13916325.00
      1867475.01     13916024.98
#Sta/Elev= 30
  4834.2 2052.82  4836.9 2052.82  4855.3 2049.97  4876.4 2047.28  4886.9 2045.16
  4908.0 2042.43  4918.6 2040.39  4971.3 2033.80  4989.7 2030.48  5002.9 2030.83
  5011.4 2029.94  5011.7 2029.44  5015.2 2029.44  5015.4 2029.94  5034.5 2031.36
  5055.6 2032.34  5097.8 2032.46  5108.3 2032.18  5129.4 2032.73  5139.9 2032.65
  5150.5 2033.12  5161.0 2033.83  5171.5 2035.45  5182.1 2036.21  5192.6 2037.40
  5203.2 2039.03  5234.8 2042.86  5266.4 2045.53  5298.0 2046.66  5308.6 2047.49
#Mann=3,-1,0
  4834.2    0.07       0  5011.4    0.05       0  5015.4    0.07       0
Bank Sta=5011.4,5015.4
Exp/Cntr=0.3,0.1

Type RM Length L Ch R = 1,317,160,160,160
BEGIN DESCRIPTION:
Mapping XS b139c068
END DESCRIPTION:
XS GIS Cut Line= 4
      1867148.82     13916577.11      1867461.02     13916548.79
      1867585.30     13916401.17      1867555.18     13916209.27
#Sta/Elev= 30
  4624.3 2061.76  4630.5 2060.80  4660.6 2058.73  4690.7 2054.38  4704.4 2053.14
  4710.8 2051.75  4730.9 2049.58  4821.3 2041.49  4901.6 2032.62  4925.5 2031.07
  4937.3 2029.35  4964.8 2027.78  4983.6 2024.83  4983.9 2024.33  4987.4 2024.33
  4987.6 2024.83  5028.5 2026.41  5049.4 2025.98  5071.4 2026.92  5078.0 2026.19
  5092.3 2026.28  5106.6 2027.21  5168.7 2028.16  5187.6 2027.48  5207.9 2028.04
  5238.2 2029.01  5268.6 2030.74  5293.9 2033.00  5309.1 2033.34  5325.0 2035.31
#Mann=3,-1,0
  4624.3    0.07       0  4983.6    0.05       0  4987.6    0.07       0
Bank Sta=4983.6,4987.6
Exp/Cntr=0.3,0.1

Type RM Length L Ch R = 1,157,0,0,0
BEGIN DESCRIPTION:
Stream0316 0.0
END DESCRIPTION:
XS GIS Cut Line= 4
      1867174.07     13916658.92      1867548.55     13916668.62
      1867655.64     13916578.14      1867664.99     13916273.89
#Sta/Elev= 30
  4540.2 2058.03  4571.1 2056.11  4621.2 2050.44  4641.2 2048.73  4651.2 2047.17
  4691.2 2043.73  4721.2 2040.20  4811.2 2031.99  4831.2 2029.61  4841.2 2029.14
  4891.2 2024.61  4922.4 2023.11  4929.0 2023.21  4943.3 2022.01  4978.4 2021.28
  4986.2 2020.19  4990.7 2020.16  4991.0 2019.66  4994.5 2019.66  4994.7 2020.16
  5007.0 2021.06  5035.6 2021.70  5053.6 2021.13  5068.2 2021.22  5118.2 2023.75
  5158.2 2024.72  5238.2 2025.09  5248.2 2026.04  5318.3 2027.81  5359.4 2029.45
#Mann=3,-1,0
  4540.2    0.07       0  4990.7    0.05       0  4994.7    0.07       0
Bank Sta=4990.7,4994.7
Exp/Cntr=0.3,0.1

Chan Stop Cuts=-1