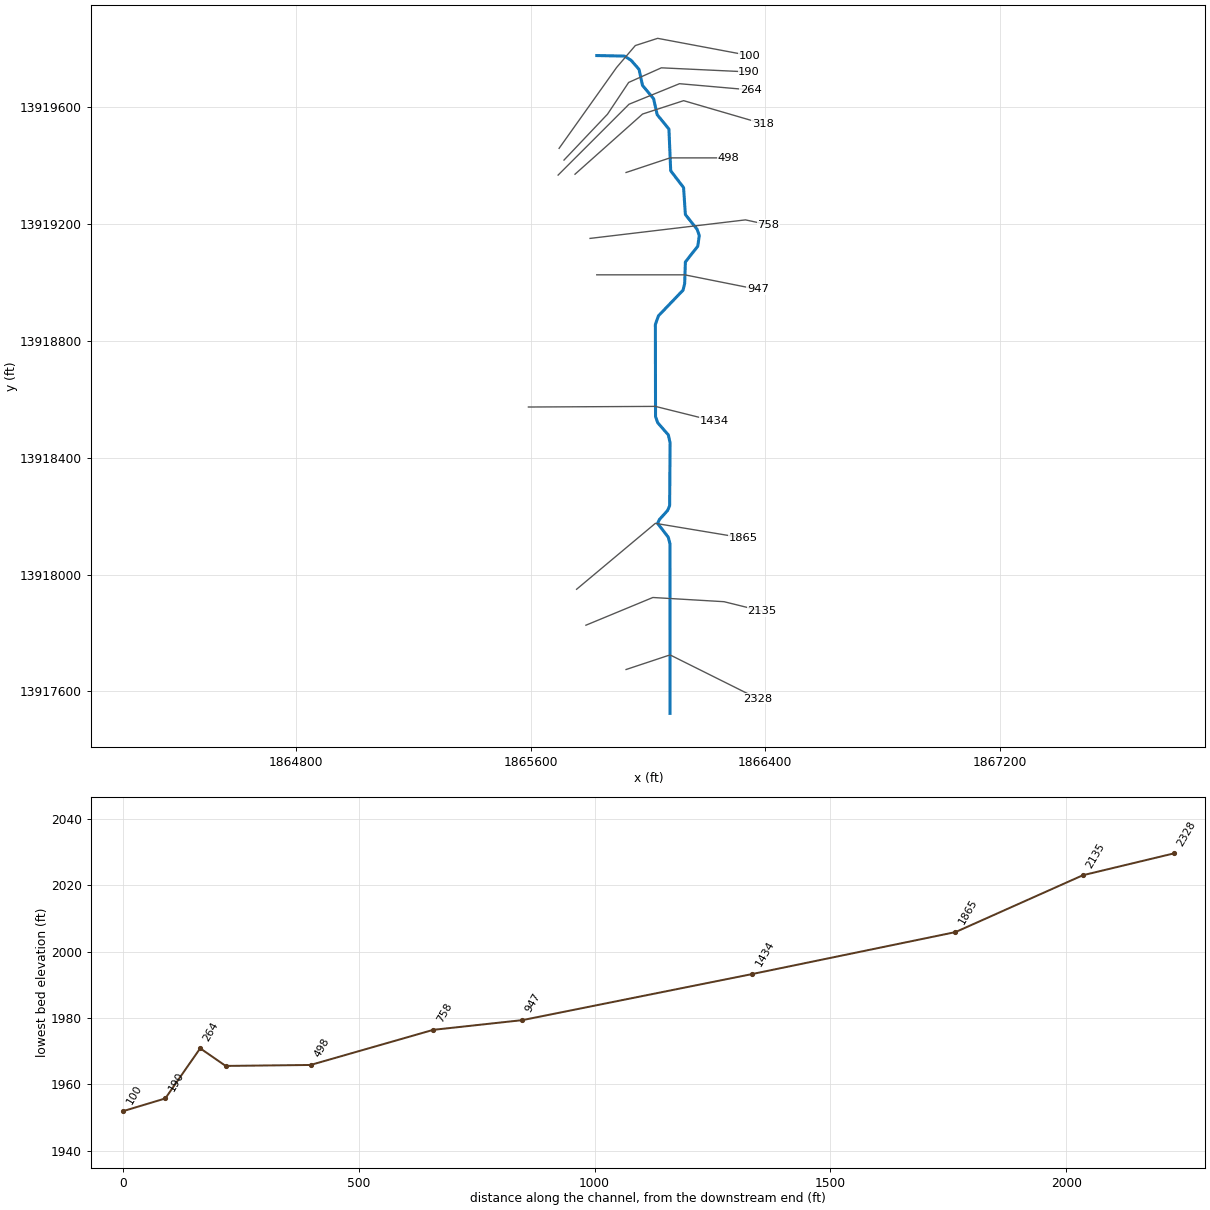
--- Stream0319.prj (project) ---

Proj Title=Stream0319 Base Level Engineering
Current Plan=p01
Default Exp/Contr=0.3,0.1
English Units
Geom File=g01
Flow File=f01
Plan File=p01
BEGIN DESCRIPTION:
Stream0319
END DESCRIPTION:

--- Stream0319.p01 (plan) ---

Plan Title=Multiple Run
Short Identifier=Multiple
Geom File=g01
Flow File=f01
Subcritical Flow
K Sum by GR= 0
Std Step Tol= 0.01
Critical Tol= 0.01
Num of Std Step Trials= 20
Max Error Tol= 0.3
Flow Tol Ratio= 0.001
Split Flow NTrial= 30
Split Flow Tol= 0.02
Split Flow Ratio= 0.02
Log Output Level= 0
Friction Slope Method= 1
Unsteady Friction Slope Method= 2
Unsteady Bridges Friction Slope Method= 1
Parabolic Critical Depth
Global Vel Dist=  1 , 1 , 1
Global Log Level= 0
CheckData=True
Encroach Param= -1, 0, 0, 0
BEGIN DESCRIPTION:
Multiple Run
END DESCRIPTION:

--- Stream0319.f01 (steady flow) ---

Flow Title=Multiple
Number of Profiles=7
Profile Names=10-year,25-year,50-year,1pct_min,100-year,1pct_plu,500-year
River Rch & RM= Stream0319,Reach-1,2328
     378     603     805     522    1041    2078    1715
Boundary for River Rch & Prof#=Stream0319,Reach-1,1
Up Type=0
Dn Type=3
Dn Slope=0.005
Boundary for River Rch & Prof#=Stream0319,Reach-1,2
Up Type=0
Dn Type=3
Dn Slope=0.005
Boundary for River Rch & Prof#=Stream0319,Reach-1,3
Up Type=0
Dn Type=3
Dn Slope=0.005
Boundary for River Rch & Prof#=Stream0319,Reach-1,4
Up Type=0
Dn Type=3
Dn Slope=0.005
Boundary for River Rch & Prof#=Stream0319,Reach-1,5
Up Type=0
Dn Type=3
Dn Slope=0.005
Boundary for River Rch & Prof#=Stream0319,Reach-1,6
Up Type=0
Dn Type=3
Dn Slope=0.005
Boundary for River Rch & Prof#=Stream0319,Reach-1,7
Up Type=0
Dn Type=3
Dn Slope=0.005

--- Stream0319.g01 (geometry) ---

Geom Title=Existing Conditions

River Reach=Stream0319,Reach-1
Reach XY= 30
      1866075.00     13917525.00      1866074.82     13918105.02
      1866068.98     13918127.45      1866032.56     13918175.00
      1866038.95     13918188.21      1866066.55     13918218.81
      1866073.62     13918235.44      1866075.20     13918450.08
      1866069.25     13918477.33      1866033.14     13918518.94
      1866025.52     13918540.22      1866024.96     13918855.02
      1866035.50     13918884.79      1866119.46     13918972.58
      1866124.87     13918995.05      1866127.38     13919069.03
      1866169.63     13919122.82      1866174.91     13919159.61
      1866167.19     13919180.92      1866127.38     13919230.97
      1866121.14     13919323.40      1866077.27     13919380.94
      1866071.24     13919523.44      1866031.12     13919572.82
      1866018.92     13919627.20      1865981.11     13919672.84
      1865969.30     13919727.58      1865942.18     13919758.74
      1865919.45     13919773.23      1865825.00     13919775.00

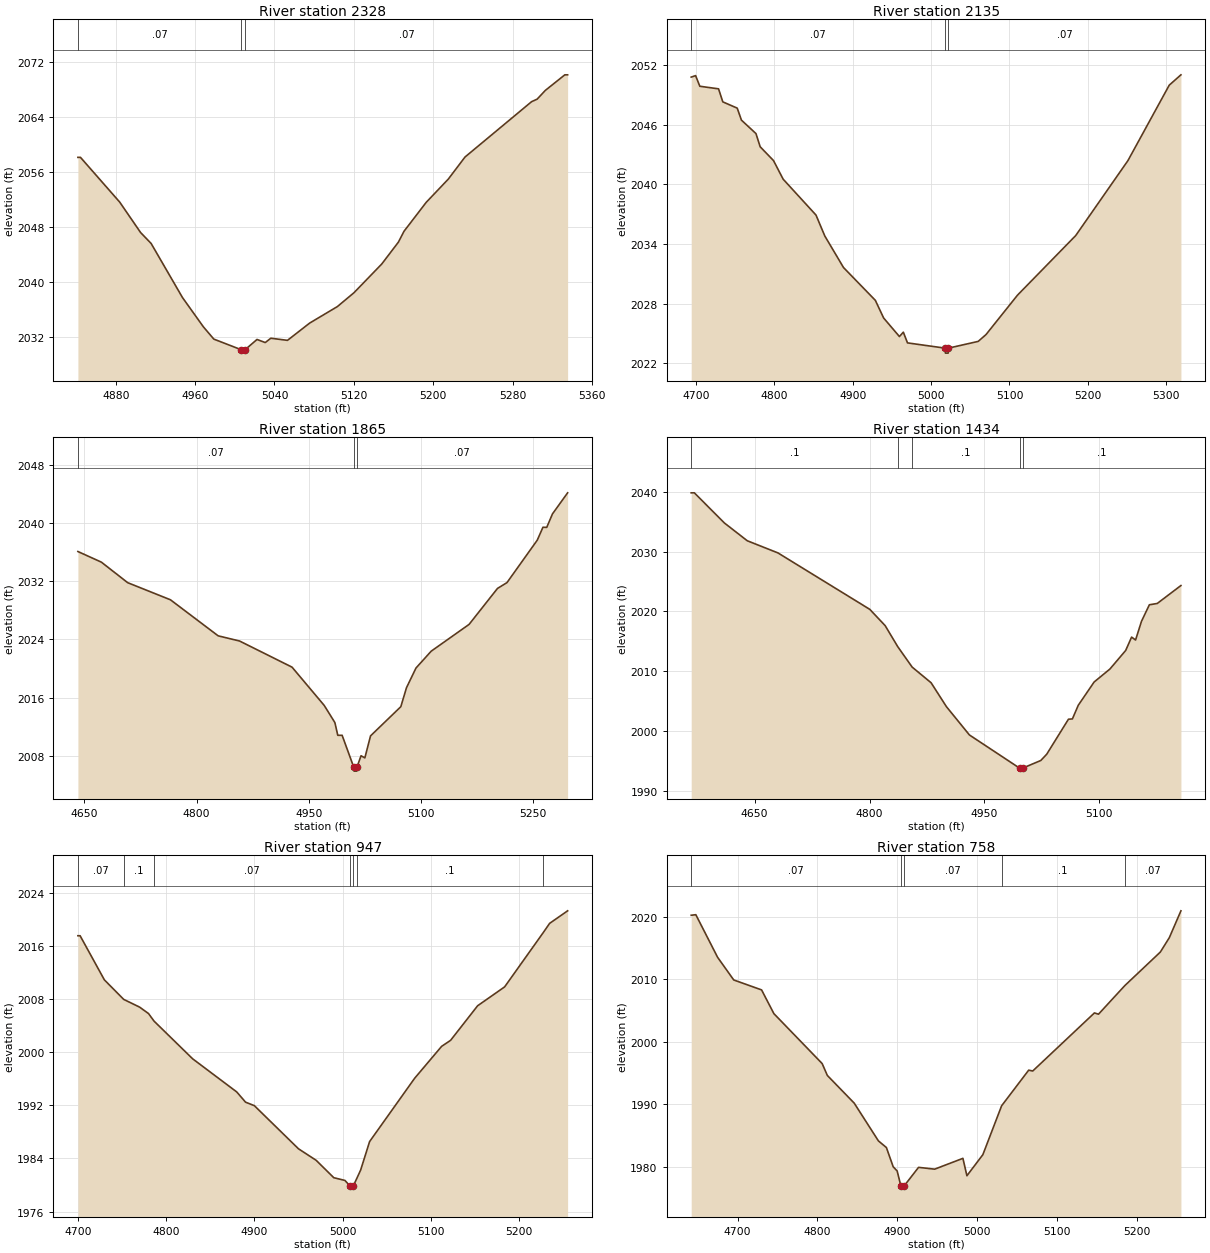
Type RM Length L Ch R = 1,2328,193,193,193
BEGIN DESCRIPTION:
Stream0319 5.0
END DESCRIPTION:
XS GIS Cut Line= 3
      1865925.02     13917675.01      1866075.00     13917725.00
      1866375.00     13917575.00
#Sta/Elev= 30
  4841.9 2058.12  4844.5 2058.12  4884.0 2051.61  4905.1 2047.17  4915.7 2045.58
  4947.3 2037.70  4968.4 2033.43  4978.9 2031.65  5006.4 2030.11  5006.6 2029.61
  5010.1 2029.61  5010.4 2030.11  5022.4 2031.60  5030.7 2031.15  5036.3 2031.78
  5053.1 2031.47  5075.5 2033.99  5103.4 2036.39  5120.2 2038.42  5148.1 2042.59
  5164.9 2045.78  5170.5 2047.35  5192.9 2051.57  5215.2 2054.96  5232.0 2058.17
  5299.1 2066.23  5304.7 2066.60  5313.0 2067.88  5332.6 2070.14  5335.4 2070.14
#Mann=3,-1,0
  4841.9    0.07       0  5006.4    0.05       0  5010.4    0.07       0
Bank Sta=5006.4,5010.4
Exp/Cntr=0.3,0.1

Type RM Length L Ch R = 1,2135,270,270,270
BEGIN DESCRIPTION:
Stream0319 4.1
END DESCRIPTION:
XS GIS Cut Line= 4
      1865788.01     13917826.56      1866016.42     13917921.36
      1866259.23     13917906.98      1866389.45     13917874.70
#Sta/Elev= 30
  4694.0 2050.80  4699.6 2050.95  4705.0 2049.88  4728.9 2049.62  4734.3 2048.31
  4752.7 2047.68  4758.1 2046.47  4776.6 2045.12  4782.0 2043.79  4799.0 2042.40
  4811.3 2040.53  4853.2 2036.92  4864.4 2034.82  4888.3 2031.64  4928.9 2028.34
  4939.5 2026.56  4959.6 2024.70  4964.6 2025.14  4969.9 2024.06  5018.0 2023.53
  5018.3 2023.03  5021.8 2023.03  5022.0 2023.53  5060.1 2024.21  5070.1 2024.90
  5110.2 2028.86  5184.5 2034.86  5251.1 2042.40  5303.8 2049.99  5318.7 2051.03
#Mann=3,-1,0
  4694.0    0.07       0  5018.0    0.05       0  5022.0    0.07       0
Bank Sta=5018,5022
Exp/Cntr=0.3,0.1

Type RM Length L Ch R = 1,1865,431,431,431
BEGIN DESCRIPTION:
Stream0319 4.0
END DESCRIPTION:
XS GIS Cut Line= 3
      1865756.22     13917949.53      1866025.00     13918175.00
      1866325.03     13918124.99
#Sta/Elev= 30
  4641.3 2036.06  4672.7 2034.60  4707.9 2031.78  4765.1 2029.43  4828.9 2024.48
  4857.5 2023.77  4927.7 2020.18  4970.7 2014.93  4985.0 2012.57  4988.9 2010.82
  4994.7 2010.82  5010.4 2006.40  5010.7 2005.90  5014.2 2005.90  5014.4 2006.40
  5020.0 2008.01  5025.1 2007.72  5032.7 2010.74  5073.2 2014.75  5080.8 2017.36
  5093.5 2020.06  5113.8 2022.37  5164.5 2026.05  5202.5 2030.99  5215.2 2031.79
  5255.7 2037.62  5263.3 2039.39  5268.4 2039.38  5276.0 2041.22  5296.3 2044.12
#Mann=3,-1,0
  4641.3    0.07       0  5010.4    0.05       0  5014.4    0.07       0
Bank Sta=5010.4,5014.4
Exp/Cntr=0.3,0.1

Type RM Length L Ch R = 1,1434,487,487,487
BEGIN DESCRIPTION:
Stream0319 3.0
END DESCRIPTION:
XS GIS Cut Line= 3
      1865591.82     13918572.86      1866025.00     13918575.00
      1866224.96     13918525.01
#Sta/Elev= 30
  4567.2 2039.82  4571.3 2039.82  4610.4 2034.79  4640.4 2031.80  4680.4 2029.77
  4800.4 2020.32  4820.4 2017.60  4836.9 2014.07  4855.6 2010.67  4880.4 2008.04
  4900.4 2004.04  4930.4 1999.31  4995.9 1993.76  4996.1 1993.26  4999.6 1993.26
  4999.9 1993.76  5023.6 1995.04  5031.3 1996.09  5059.7 2001.95  5064.8 2001.99
  5072.5 2004.28  5093.2 2008.17  5113.8 2010.34  5134.4 2013.45  5142.1 2015.68
  5147.3 2015.20  5155.0 2018.32  5165.3 2021.09  5175.6 2021.31  5206.5 2024.31
#Mann=5,-1,0
  4567.2     0.1       0  4836.9    0.07       0  4855.6     0.1       0
  4995.9    0.05       0  4999.9     0.1       0
Bank Sta=4995.9,4999.9
Exp/Cntr=0.3,0.1

Type RM Length L Ch R = 1,947,189,189,189
BEGIN DESCRIPTION:
Stream0319 2.0
END DESCRIPTION:
XS GIS Cut Line= 3
      1865824.96     13919025.00      1866125.00     13919025.00
      1866375.00     13918975.00
#Sta/Elev= 30
  4699.9 2017.52  4702.4 2017.52  4729.9 2010.88  4751.8 2007.94  4769.9 2006.77
  4779.9 2005.81  4786.2 2004.67  4829.9 1999.00  4879.9 1994.01  4889.9 1992.47
  4899.9 1991.94  4949.9 1985.45  4969.9 1983.72  4989.9 1981.10  5002.5 1980.69
  5008.1 1979.88  5008.4 1979.38  5011.9 1979.38  5012.1 1979.88  5015.9 1980.97
  5020.3 1982.24  5030.5 1986.54  5081.5 1996.06  5112.1 2000.87  5122.3 2001.78
  5152.9 2006.98  5183.5 2009.82  5227.2 2017.98  5234.5 2019.38  5254.9 2021.27
#Mann=7,-1,0
  4699.9    0.07       0  4751.8     0.1       0  4786.2    0.07       0
  5008.1    0.05       0  5012.1    0.07       0  5015.9     0.1       0
  5227.2    0.07       0
Bank Sta=5008.1,5012.1
Exp/Cntr=0.3,0.1

Type RM Length L Ch R = 1,758,260,260,260
BEGIN DESCRIPTION:
Stream0319 1.1
END DESCRIPTION:
XS GIS Cut Line= 3
      1865802.10     13919149.57      1866332.36     13919212.94
      1866410.22     13919196.06
#Sta/Elev= 30
  4641.8 2020.22  4647.6 2020.31  4674.9 2013.50  4695.1 2009.88  4730.0 2008.29
  4745.4 2004.50  4805.9 1996.52  4812.4 1994.62  4846.1 1990.19  4876.4 1984.16
  4886.4 1983.10  4894.9 1980.03  4899.9 1979.35  4904.6 1976.95  4904.8 1976.45
  4908.6 1976.95  4926.7 1979.93  4946.9 1979.64  4982.3 1981.37  4987.3 1978.59
  5007.3 1981.96  5030.8 1989.77  5064.7 1995.46  5069.8 1995.33  5147.1 2004.61
  5152.2 2004.41  5185.2 2008.98  5229.7 2014.34  5241.0 2016.65  5255.5 2020.93
#Mann=5,-1,0
  4641.8    0.07       0  4904.6    0.05       0  4908.6    0.07       0
  5030.8     0.1       0  5185.2    0.07       0
Bank Sta=4904.6,4908.6
Exp/Cntr=0.3,0.1

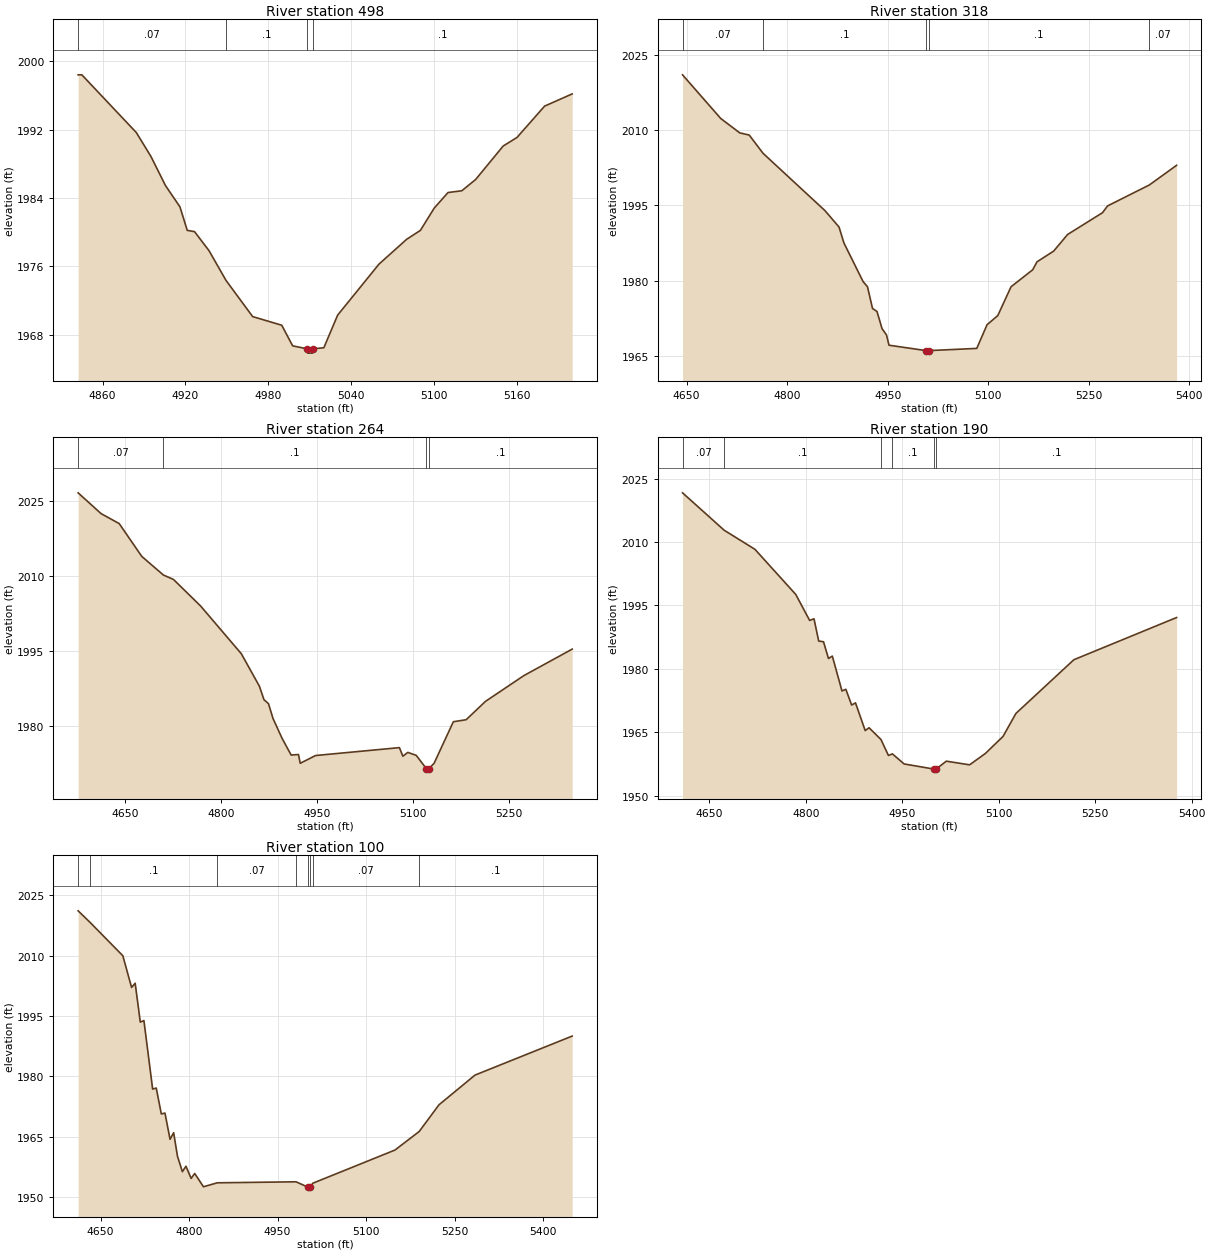
Type RM Length L Ch R = 1,498,180,180,180
BEGIN DESCRIPTION:
Stream0319 1.0
END DESCRIPTION:
XS GIS Cut Line= 3
      1865924.97     13919374.99      1866075.00     13919425.00
      1866274.95     13919425.00
#Sta/Elev= 30
  4842.2 1998.40  4844.9 1998.40  4884.4 1991.65  4894.9 1988.88  4905.5 1985.46
  4916.0 1982.97  4921.3 1980.22  4926.6 1980.07  4937.1 1977.84  4949.4 1974.37
  4968.7 1970.14  4989.8 1969.13  4997.7 1966.72  5008.3 1966.37  5008.6 1965.87
  5012.1 1965.87  5012.3 1966.37  5020.3 1966.50  5030.3 1970.31  5060.3 1976.28
  5080.3 1979.17  5090.3 1980.22  5100.3 1982.82  5110.3 1984.64  5120.3 1984.85
  5130.3 1986.16  5150.3 1990.08  5160.3 1991.08  5180.3 1994.74  5200.3 1996.17
#Mann=4,-1,0
  4842.2    0.07       0  4949.4     0.1       0  5008.3    0.05       0
  5012.3     0.1       0
Bank Sta=5008.3,5012.3
Exp/Cntr=0.3,0.1

Type RM Length L Ch R = 1,318,54,54,54
BEGIN DESCRIPTION:
Mapping XS 6ed8caa1
END DESCRIPTION:
XS GIS Cut Line= 4
      1865750.73     13919369.12      1865981.18     13919574.91
      1866121.39     13919620.70      1866391.12     13919541.79
#Sta/Elev= 30
  4643.8 2021.01  4700.8 2012.32  4729.2 2009.45  4743.4 2009.01  4764.0 2005.38
  4856.3 1993.98  4877.4 1990.70  4884.7 1987.53  4913.2 1979.86  4919.9 1978.80
  4927.4 1974.48  4934.1 1973.87  4941.6 1970.47  4948.3 1969.19  4952.0 1967.16
  5007.4 1966.08  5007.6 1965.58  5011.4 1966.08  5083.0 1966.52  5098.4 1971.24
  5114.4 1973.06  5134.2 1978.80  5166.5 1982.18  5172.9 1983.76  5197.8 1985.90
  5218.6 1989.21  5270.7 1993.55  5278.4 1994.91  5340.6 1999.07  5381.3 2002.99
#Mann=5,-1,0
  4643.8    0.07       0  4764.0     0.1       0  5007.4    0.05       0
  5011.4     0.1       0  5340.6    0.07       0
Bank Sta=5007.4,5011.4
Exp/Cntr=0.3,0.1

Type RM Length L Ch R = 1,264,74,74,74
BEGIN DESCRIPTION:
Stream0319 0.0
END DESCRIPTION:
XS GIS Cut Line= 4
      1865693.14     13919366.14      1865935.06     13919608.48
      1866107.23     13919678.71      1866350.02     13919657.41
#Sta/Elev= 30
  4576.5 2026.55  4612.4 2022.39  4640.7 2020.40  4676.0 2013.83  4709.8 2010.11
  4725.5 2009.23  4767.9 2003.92  4831.6 1994.36  4859.9 1987.85  4866.9 1985.19
  4874.0 1984.38  4881.1 1981.41  4895.2 1977.46  4909.4 1974.11  4920.9 1974.21
  4923.6 1972.46  4947.6 1974.01  5078.6 1975.59  5084.0 1973.87  5091.7 1974.64
  5104.9 1974.04  5120.7 1971.39  5121.0 1970.89  5124.7 1971.39  5132.8 1972.46
  5162.9 1980.77  5182.9 1981.17  5213.1 1984.84  5273.3 1990.01  5348.6 1995.29
#Mann=4,-1,0
  4576.5    0.07       0  4709.8     0.1       0  5120.7    0.05       0
  5124.7     0.1       0
Bank Sta=5120.7,5124.7
Exp/Cntr=0.3,0.1

Type RM Length L Ch R = 1,190,90,90,90
BEGIN DESCRIPTION:
Mapping XS 7ac5b846
END DESCRIPTION:
XS GIS Cut Line= 5
      1865713.25     13919417.52      1865861.55     13919574.30
      1865933.82     13919683.03      1866045.40     13919733.02
      1866344.54     13919718.93
#Sta/Elev= 30
  4608.5 2021.68  4673.2 2012.83  4721.1 2008.30  4784.6 1997.61  4806.1 1991.47
  4812.9 1991.85  4820.2 1986.58  4827.7 1986.41  4835.4 1982.45  4841.4 1983.02
  4856.4 1974.76  4862.4 1975.16  4871.4 1971.43  4877.4 1971.95  4892.5 1965.38
  4898.5 1966.05  4917.0 1963.27  4928.6 1959.49  4934.8 1959.86  4953.0 1957.48
  4998.9 1956.28  4999.2 1955.78  5002.9 1956.28  5018.6 1958.14  5054.8 1957.27
  5079.4 1959.97  5106.8 1964.00  5126.8 1969.44  5216.9 1982.16  5376.6 1992.15
#Mann=6,-1,0
  4608.5    0.07       0  4673.2     0.1       0  4917.0    0.07       0
  4934.8     0.1       0  4998.9    0.05       0  5002.9     0.1       0
Bank Sta=4998.9,5002.9
Exp/Cntr=0.3,0.1

Type RM Length L Ch R = 1,100,0,0,0
BEGIN DESCRIPTION:
Stream0319 0.1
END DESCRIPTION:
XS GIS Cut Line= 5
      1865696.51     13919457.63      1865892.79     13919734.34
      1865956.56     13919809.22      1866032.73     13919833.88
      1866346.85     13919774.79
#Sta/Elev= 30
  4612.0 2021.12  4632.1 2018.27  4687.8 2009.95  4702.6 2002.07  4708.7 2003.12
  4717.4 1993.45  4723.5 1993.84  4738.3 1976.81  4744.4 1977.06  4753.0 1970.62
  4759.2 1970.84  4767.8 1964.31  4773.9 1965.95  4780.4 1960.09  4788.7 1956.27
  4794.8 1957.62  4803.5 1954.59  4809.6 1955.82  4824.4 1952.52  4847.8 1953.50
  4981.3 1953.75  5001.4 1952.43  5001.6 1951.93  5005.4 1952.43  5009.8 1953.40
  5148.9 1961.64  5190.0 1966.25  5223.6 1972.90  5284.6 1980.28  5449.3 1989.98
#Mann=8,-1,0
  4612.0    0.07       0  4632.1     0.1       0  4847.8    0.07       0
  4981.3     0.1       0  5001.4    0.05       0  5005.4     0.1       0
  5009.8    0.07       0  5190.0     0.1       0
Bank Sta=5001.4,5005.4
Exp/Cntr=0.3,0.1

Chan Stop Cuts=-1