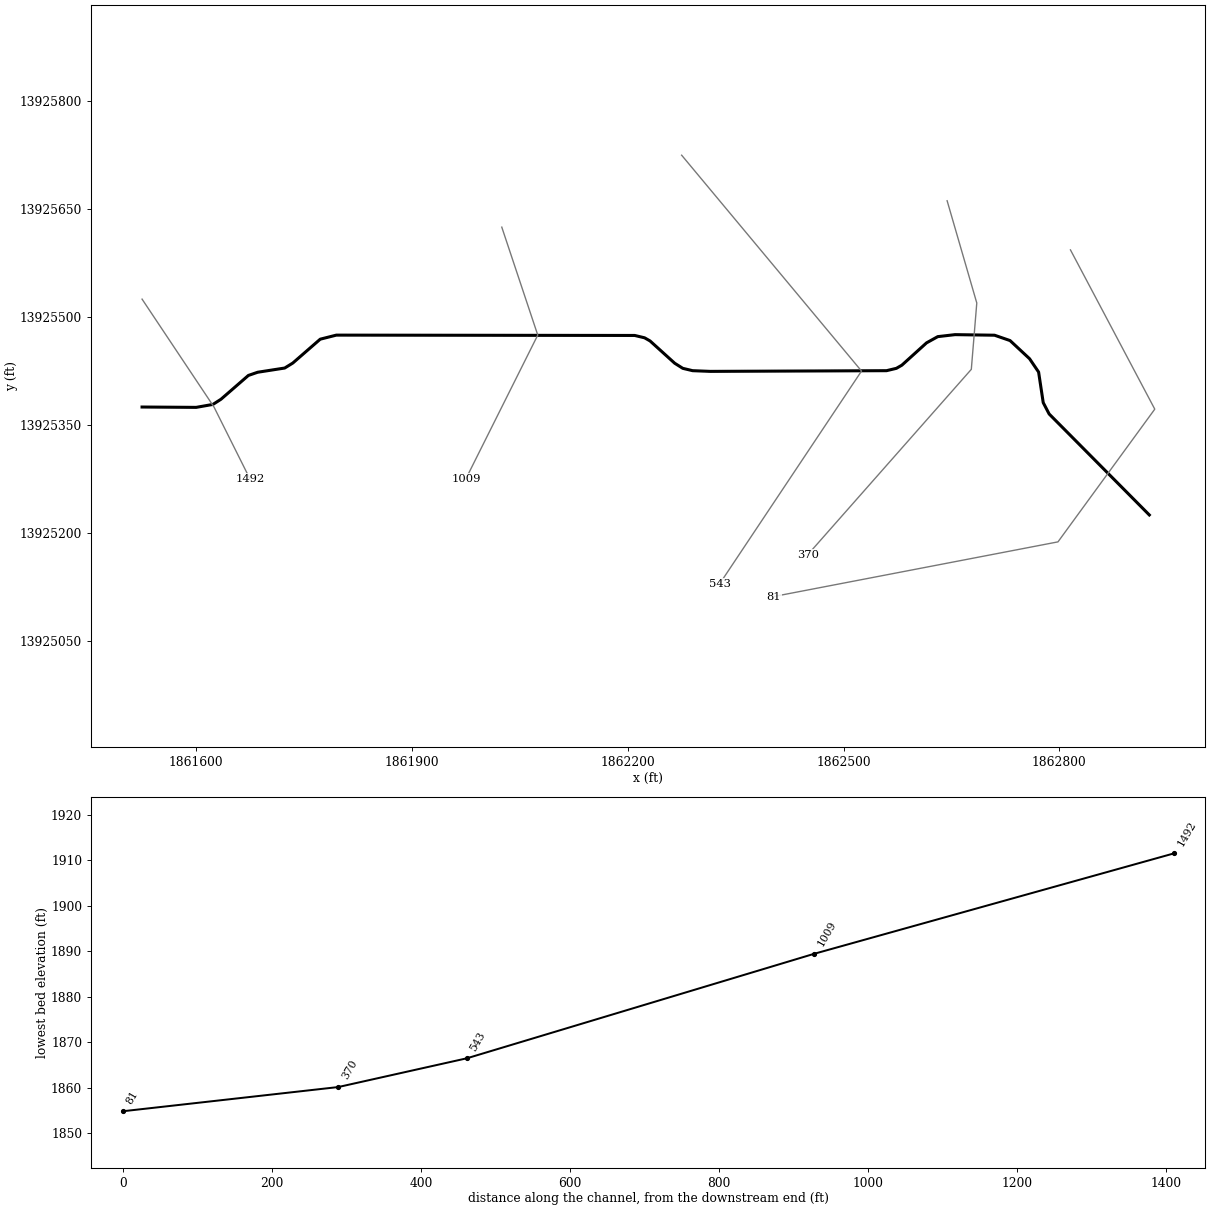
--- Stream0320.prj (project) ---

Proj Title=Stream0320 Base Level Engineering
Current Plan=p01
Default Exp/Contr=0.3,0.1
English Units
Geom File=g01
Flow File=f01
Plan File=p01
BEGIN DESCRIPTION:
Stream0320
END DESCRIPTION:

--- Stream0320.p01 (plan) ---

Plan Title=Multiple Run
Short Identifier=Multiple
Geom File=g01
Flow File=f01
Subcritical Flow
K Sum by GR= 0
Std Step Tol= 0.01
Critical Tol= 0.01
Num of Std Step Trials= 20
Max Error Tol= 0.3
Flow Tol Ratio= 0.001
Split Flow NTrial= 30
Split Flow Tol= 0.02
Split Flow Ratio= 0.02
Log Output Level= 0
Friction Slope Method= 1
Unsteady Friction Slope Method= 2
Unsteady Bridges Friction Slope Method= 1
Parabolic Critical Depth
Global Vel Dist=  1 , 1 , 1
Global Log Level= 0
CheckData=True
Encroach Param= -1, 0, 0, 0
BEGIN DESCRIPTION:
Multiple Run
END DESCRIPTION:

--- Stream0320.f01 (steady flow) ---

Flow Title=Multiple
Number of Profiles=7
Profile Names=10-year,25-year,50-year,1pct_min,100-year,1pct_plu,500-year
River Rch & RM= Stream0320,Reach-1,1492
     295     465     616     398     793    1583    1291
Boundary for River Rch & Prof#=Stream0320,Reach-1,1
Up Type=0
Dn Type=3
Dn Slope=0.005
Boundary for River Rch & Prof#=Stream0320,Reach-1,2
Up Type=0
Dn Type=3
Dn Slope=0.005
Boundary for River Rch & Prof#=Stream0320,Reach-1,3
Up Type=0
Dn Type=3
Dn Slope=0.005
Boundary for River Rch & Prof#=Stream0320,Reach-1,4
Up Type=0
Dn Type=3
Dn Slope=0.005
Boundary for River Rch & Prof#=Stream0320,Reach-1,5
Up Type=0
Dn Type=3
Dn Slope=0.005
Boundary for River Rch & Prof#=Stream0320,Reach-1,6
Up Type=0
Dn Type=3
Dn Slope=0.005
Boundary for River Rch & Prof#=Stream0320,Reach-1,7
Up Type=0
Dn Type=3
Dn Slope=0.005

--- Stream0320.g01 (geometry) ---

Geom Title=Existing Conditions

River Reach=Stream0320,Reach-1
Reach XY= 30
      1861525.00     13925375.00      1861600.20     13925374.52
      1861623.50     13925378.63      1861634.67     13925385.79
      1861672.81     13925418.91      1861685.69     13925423.34
      1861723.27     13925429.19      1861734.53     13925436.14
      1861772.65     13925469.29      1861795.03     13925474.94
      1862209.78     13925474.48      1862223.43     13925471.22
      1862231.06     13925466.86      1862265.35     13925435.85
      1862276.57     13925428.78      1862290.22     13925425.52
      1862314.81     13925424.55      1862559.78     13925425.52
      1862573.44     13925428.78      1862581.06     13925433.15
      1862615.37     13925464.19      1862630.98     13925472.84
      1862654.97     13925475.61      1862709.91     13925474.81
      1862731.45     13925467.36      1862758.54     13925442.15
      1862771.13     13925423.60      1862777.55     13925381.09
      1862785.78     13925365.34      1862925.00     13925225.00

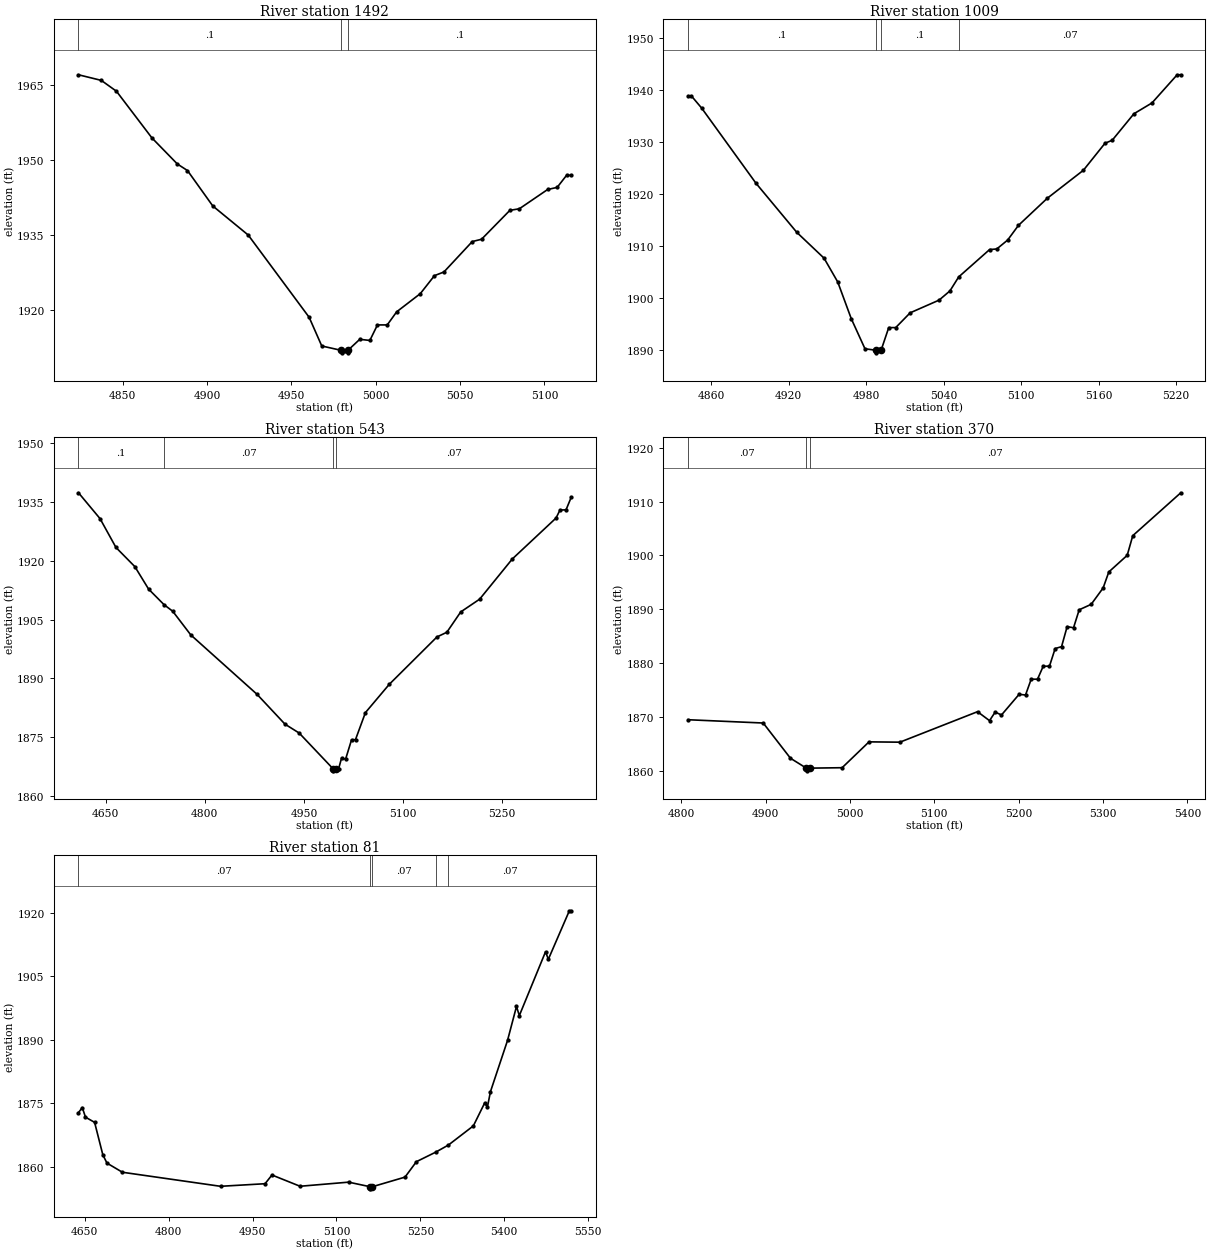
Type RM Length L Ch R = 1,1492,483,483,483
BEGIN DESCRIPTION:
Stream0320 3.0
END DESCRIPTION:
XS GIS Cut Line= 3
      1861525.02     13925524.97      1861625.00     13925375.00
      1861675.02     13925274.96
#Sta/Elev= 30
  4823.8 1967.08  4837.3 1965.96  4846.3 1963.79  4867.3 1954.47  4882.4 1949.25
  4888.4 1947.94  4903.4 1940.86  4924.4 1935.05  4960.5 1918.62  4968.0 1912.88
  4979.5 1912.01  4979.8 1911.51  4983.3 1911.51  4983.5 1912.01  4990.5 1914.21
  4996.5 1913.99  5001.0 1917.09  5006.8 1917.09  5012.4 1919.71  5026.4 1923.34
  5034.8 1926.94  5040.4 1927.67  5057.2 1933.75  5062.7 1934.21  5079.5 1939.99
  5085.1 1940.30  5101.9 1944.16  5107.5 1944.57  5113.1 1946.99  5115.9 1946.99
#Mann=3,-1,0
  4823.8     0.1       0  4979.5    0.05       0  4983.5     0.1       0
Bank Sta=4979.5,4983.5
Exp/Cntr=0.3,0.1

Type RM Length L Ch R = 1,1009,466,466,466
BEGIN DESCRIPTION:
Stream0320 2.0
END DESCRIPTION:
XS GIS Cut Line= 3
      1862024.99     13925625.02      1862075.00     13925475.00
      1861975.02     13925275.04
#Sta/Elev= 30
  4841.9 1938.77  4844.6 1938.77  4852.5 1936.45  4894.6 1922.00  4926.2 1912.57
  4947.3 1907.61  4957.9 1903.04  4968.4 1895.97  4979.0 1890.20  4987.5 1889.92
  4987.7 1889.42  4991.5 1889.92  4997.4 1894.27  5002.8 1894.27  5014.0 1897.11
  5036.4 1899.55  5044.8 1901.32  5051.6 1904.01  5075.5 1909.26  5081.1 1909.38
  5089.5 1911.09  5097.9 1913.92  5120.2 1919.12  5148.2 1924.51  5164.9 1929.69
  5170.5 1930.27  5187.3 1935.36  5201.3 1937.44  5220.8 1942.85  5223.6 1942.85
#Mann=4,-1,0
  4841.9     0.1       0  4987.5    0.05       0  4991.5     0.1       0
  5051.6    0.07       0
Bank Sta=4987.5,4991.5
Exp/Cntr=0.3,0.1

Type RM Length L Ch R = 1,543,173,173,173
BEGIN DESCRIPTION:
Stream0320 1.0
END DESCRIPTION:
XS GIS Cut Line= 3
      1862274.98     13925725.02      1862525.00     13925425.00
      1862328.02     13925129.59
#Sta/Elev= 30
  4609.0 1937.31  4641.6 1930.72  4665.7 1923.37  4694.3 1918.48  4715.1 1912.75
  4738.5 1908.78  4751.6 1907.11  4778.9 1901.08  4879.1 1885.95  4921.4 1878.34
  4942.9 1876.07  4994.3 1866.94  4994.5 1866.44  4998.3 1866.94  5002.5 1866.94
  5007.1 1869.74  5013.1 1869.41  5022.1 1874.34  5028.1 1874.40  5043.1 1881.28
  5079.2 1888.49  5151.3 1900.56  5166.3 1901.76  5187.3 1906.94  5215.9 1910.19
  5265.4 1920.45  5331.5 1930.87  5337.5 1932.92  5346.6 1932.95  5354.6 1936.21
#Mann=4,-1,0
  4609.0     0.1       0  4738.5    0.07       0  4994.3    0.05       0
  4998.3    0.07       0
Bank Sta=4994.3,4998.3
Exp/Cntr=0.3,0.1

Type RM Length L Ch R = 1,370,289,289,289
BEGIN DESCRIPTION:
Stream0320 0.1
END DESCRIPTION:
XS GIS Cut Line= 4
      1862643.98     13925661.71      1862685.20     13925519.61
      1862677.60     13925427.38      1862450.27     13925169.73
#Sta/Elev= 30
  4808.1 1869.57  4897.3 1868.96  4929.6 1862.43  4948.4 1860.60  4948.7 1860.10
  4952.4 1860.60  4990.8 1860.68  5022.7 1865.47  5059.3 1865.41  5151.3 1871.06
  5165.5 1869.40  5172.2 1870.98  5179.7 1870.45  5200.6 1874.28  5208.2 1874.15
  5214.9 1877.08  5222.4 1877.08  5229.1 1879.46  5236.6 1879.51  5243.3 1882.76
  5250.9 1883.11  5257.5 1886.82  5265.1 1886.61  5271.8 1889.94  5286.0 1890.95
  5300.2 1893.99  5306.9 1896.95  5328.7 1900.03  5335.3 1903.67  5392.2 1911.62
#Mann=3,-1,0
  4808.1    0.07       0  4948.4    0.05       0  4952.4    0.07       0
Bank Sta=4948.4,4952.4
Exp/Cntr=0.3,0.1

Type RM Length L Ch R = 1,81,0,0,0
BEGIN DESCRIPTION:
Stream0320 0.0
END DESCRIPTION:
XS GIS Cut Line= 4
      1862815.40     13925593.41      1862932.60     13925372.04
      1862798.05     13925187.58      1862403.08     13925111.63
#Sta/Elev= 30
  4638.8 1872.80  4645.6 1873.99  4651.3 1871.72  4667.6 1870.49  4682.3 1862.83
  4689.7 1860.86  4717.3 1858.70  4892.7 1855.38  4972.3 1855.99  4984.7 1858.05
  5034.9 1855.39  5121.7 1856.36  5160.1 1855.28  5160.4 1854.78  5164.1 1855.28
  5222.5 1857.55  5242.9 1861.20  5277.1 1863.43  5300.1 1865.13  5344.7 1869.66
  5364.8 1875.04  5369.9 1874.17  5375.3 1877.76  5405.8 1889.86  5421.8 1897.88
  5426.9 1895.73  5473.7 1910.80  5478.8 1909.05  5516.3 1920.50  5519.8 1920.50
#Mann=5,-1,0
  4638.8    0.07       0  5160.1    0.05       0  5164.1    0.07       0
  5277.1     0.1       0  5300.1    0.07       0
Bank Sta=5160.1,5164.1
Exp/Cntr=0.3,0.1

Chan Stop Cuts=-1