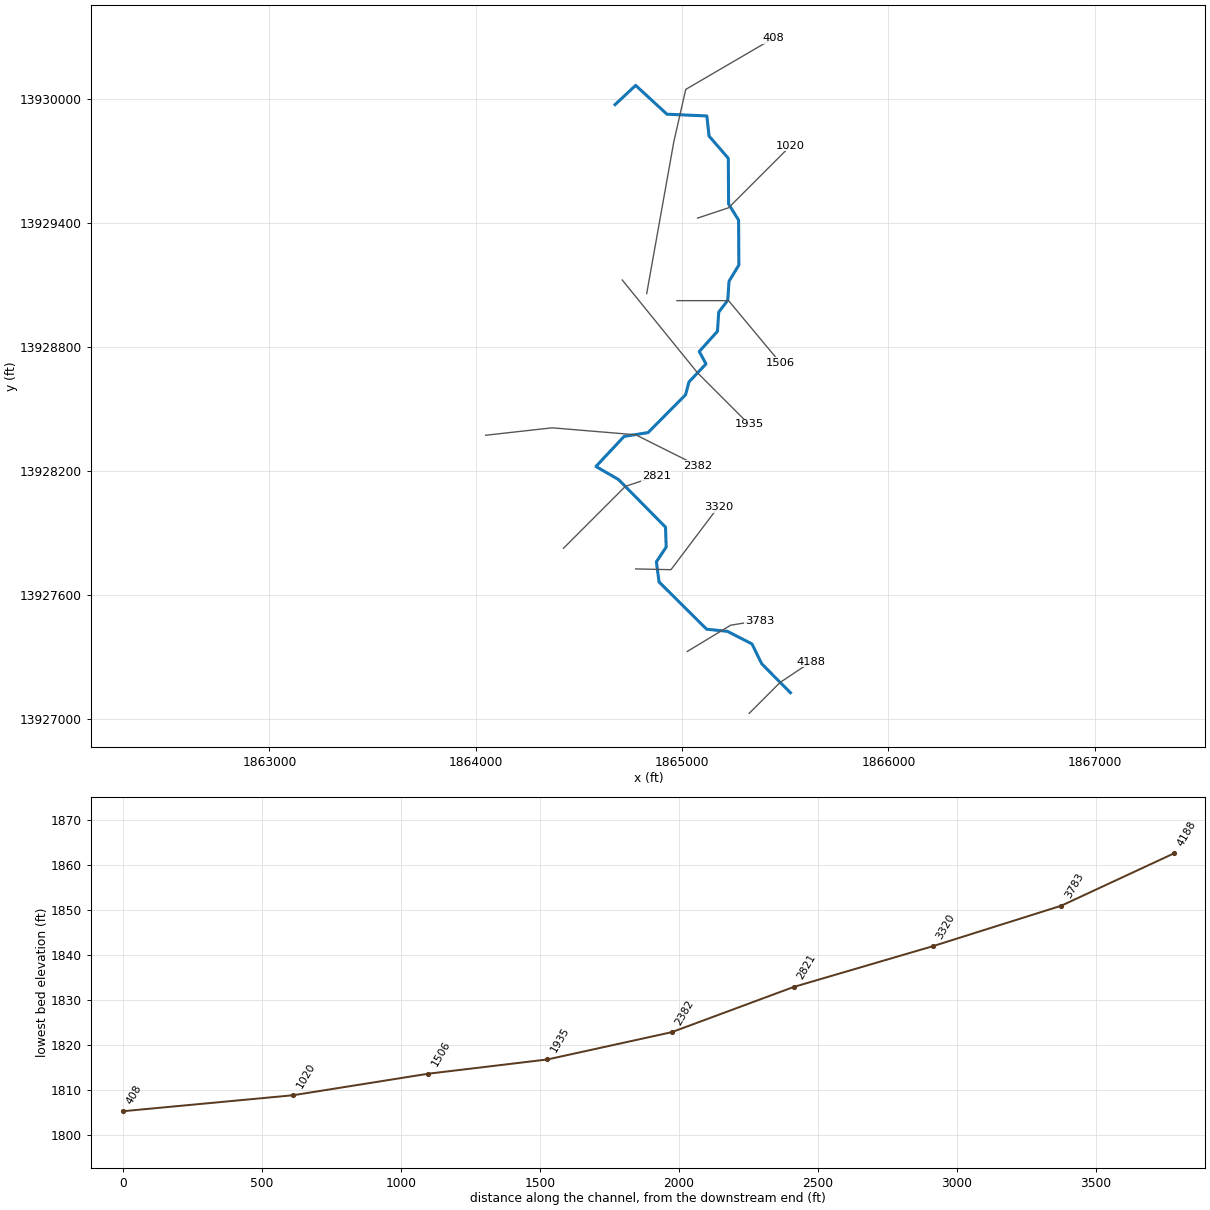
--- Stream0321.prj (project) ---

Proj Title=Stream0321 Base Level Engineering
Current Plan=p01
Default Exp/Contr=0.3,0.1
English Units
Geom File=g01
Flow File=f01
Plan File=p01
BEGIN DESCRIPTION:
Stream0321
END DESCRIPTION:

--- Stream0321.p01 (plan) ---

Plan Title=Multiple Run
Short Identifier=Multiple
Geom File=g01
Flow File=f01
Subcritical Flow
K Sum by GR= 0
Std Step Tol= 0.01
Critical Tol= 0.01
Num of Std Step Trials= 20
Max Error Tol= 0.3
Flow Tol Ratio= 0.001
Split Flow NTrial= 30
Split Flow Tol= 0.02
Split Flow Ratio= 0.02
Log Output Level= 0
Friction Slope Method= 1
Unsteady Friction Slope Method= 2
Unsteady Bridges Friction Slope Method= 1
Parabolic Critical Depth
Global Vel Dist=  1 , 1 , 1
Global Log Level= 0
CheckData=True
Encroach Param= -1, 0, 0, 0
BEGIN DESCRIPTION:
Multiple Run
END DESCRIPTION:

--- Stream0321.f01 (steady flow) ---

Flow Title=Multiple
Number of Profiles=7
Profile Names=10-year,25-year,50-year,1pct_min,100-year,1pct_plu,500-year
River Rch & RM= Stream0321,Reach-1,4188
     801    1349    1867    1252    2498    4983    4409
Boundary for River Rch & Prof#=Stream0321,Reach-1,1
Up Type=0
Dn Type=3
Dn Slope=0.005
Boundary for River Rch & Prof#=Stream0321,Reach-1,2
Up Type=0
Dn Type=3
Dn Slope=0.005
Boundary for River Rch & Prof#=Stream0321,Reach-1,3
Up Type=0
Dn Type=3
Dn Slope=0.005
Boundary for River Rch & Prof#=Stream0321,Reach-1,4
Up Type=0
Dn Type=3
Dn Slope=0.005
Boundary for River Rch & Prof#=Stream0321,Reach-1,5
Up Type=0
Dn Type=3
Dn Slope=0.005
Boundary for River Rch & Prof#=Stream0321,Reach-1,6
Up Type=0
Dn Type=3
Dn Slope=0.005
Boundary for River Rch & Prof#=Stream0321,Reach-1,7
Up Type=0
Dn Type=3
Dn Slope=0.005

--- Stream0321.g01 (geometry) ---

Geom Title=Existing Conditions

River Reach=Stream0321,Reach-1
Reach XY= 30
      1865525.00     13927125.00      1865385.78     13927265.34
      1865338.57     13927361.53      1865219.44     13927422.55
      1865118.83     13927432.86      1864888.34     13927661.70
      1864875.38     13927759.72      1864922.83     13927830.98
      1864919.60     13927927.43      1864691.65     13928158.35
      1864582.48     13928221.42      1864718.83     13928367.14
      1864834.79     13928385.52      1865016.84     13928568.95
      1865033.20     13928631.05      1865115.68     13928718.34
      1865083.02     13928778.33      1865171.36     13928876.50
      1865177.47     13928969.43      1865221.15     13929026.60
      1865227.36     13929119.02      1865275.10     13929197.69
      1865273.62     13929415.34      1865225.21     13929493.27
      1865223.94     13929714.56      1865130.57     13929822.65
      1865119.92     13929919.97      1864926.47     13929928.54
      1864775.00     13930068.03      1864675.00     13929975.00

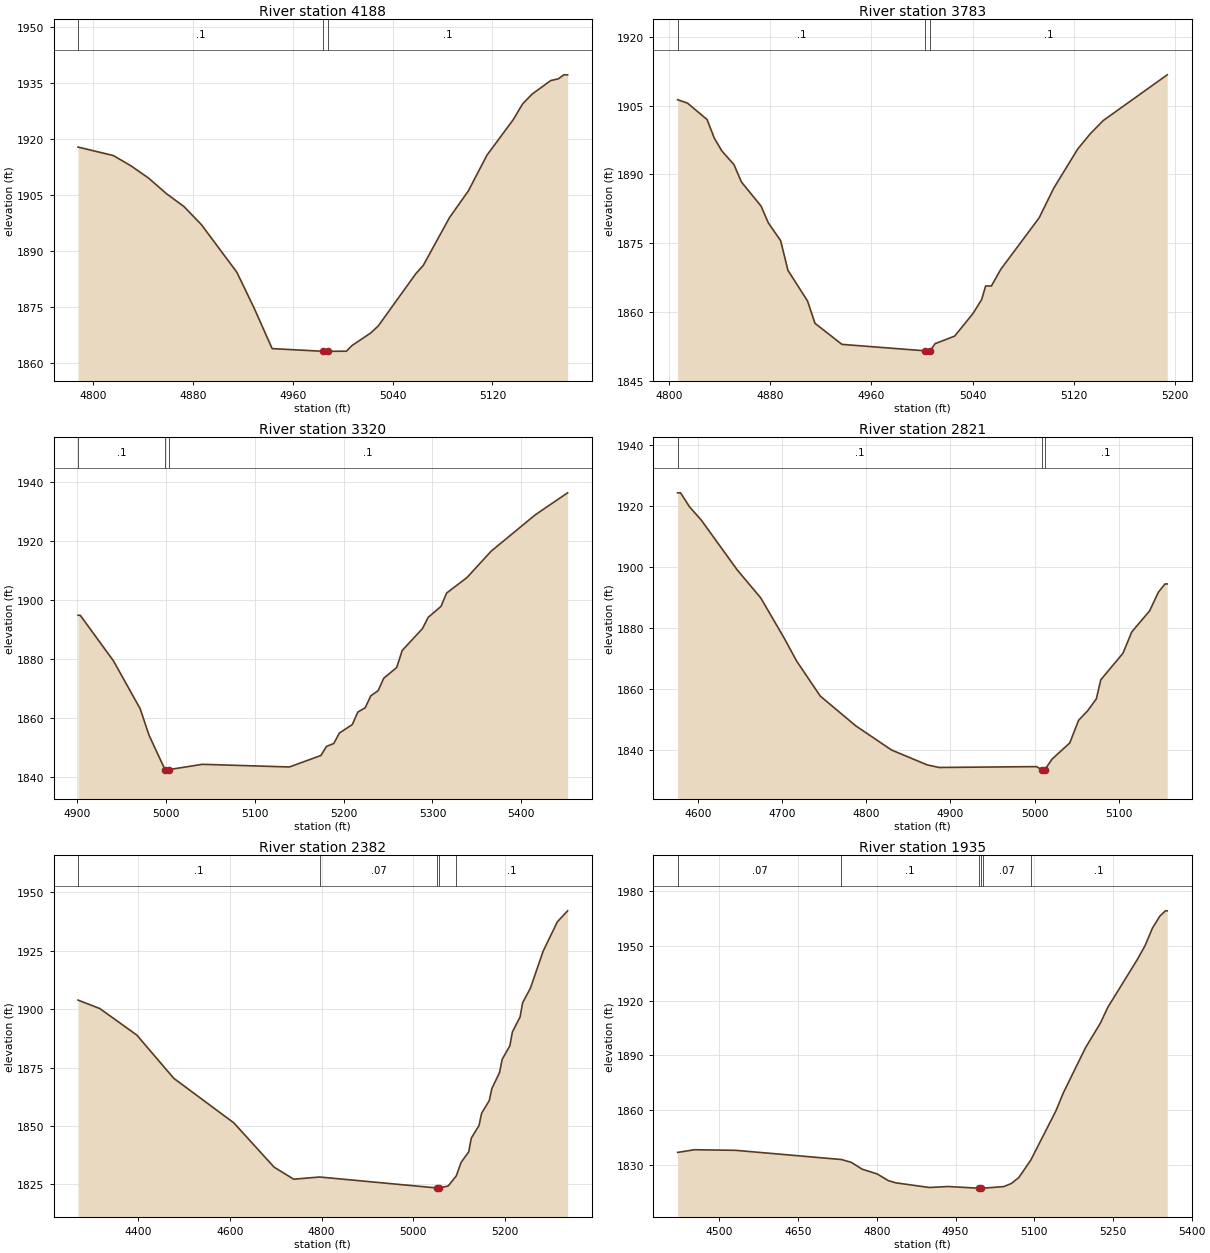
Type RM Length L Ch R = 1,4188,405,405,405
BEGIN DESCRIPTION:
Stream0321 8.0
END DESCRIPTION:
XS GIS Cut Line= 3
      1865325.00     13927025.00      1865475.00     13927175.00
      1865624.99     13927274.99
#Sta/Elev= 30
  4787.9 1917.88  4816.2 1915.61  4830.3 1912.86  4844.5 1909.55  4858.6 1905.44
  4872.8 1901.94  4886.9 1897.05  4915.2 1884.33  4929.3 1874.54  4943.5 1863.86
  4983.9 1863.15  4984.1 1862.65  4987.6 1862.65  4987.9 1863.15  5003.0 1863.16
  5007.5 1864.68  5022.6 1868.08  5028.6 1869.96  5058.6 1883.92  5064.6 1886.16
  5085.7 1899.01  5100.7 1906.10  5115.7 1915.73  5136.7 1925.21  5144.3 1929.48
  5151.8 1932.06  5166.8 1935.71  5172.8 1936.16  5177.3 1937.24  5180.3 1937.24
#Mann=3,-1,0
  4787.9     0.1       0  4983.9    0.05       0  4987.9     0.1       0
Bank Sta=4983.9,4987.9
Exp/Cntr=0.3,0.1

Type RM Length L Ch R = 1,3783,463,463,463
BEGIN DESCRIPTION:
Stream0321 7.0
END DESCRIPTION:
XS GIS Cut Line= 3
      1865024.96     13927324.98      1865235.33     13927452.31
      1865374.99     13927475.00
#Sta/Elev= 30
  4806.6 1906.28  4814.4 1905.55  4829.9 1901.96  4835.7 1897.87  4841.7 1895.08
  4851.2 1892.13  4857.1 1888.34  4872.6 1883.10  4878.4 1879.42  4888.1 1875.56
  4893.9 1869.08  4909.4 1862.40  4915.3 1857.53  4936.6 1852.94  5002.5 1851.53
  5002.7 1851.03  5006.5 1851.53  5010.3 1853.09  5025.8 1854.74  5040.4 1859.70
  5047.2 1862.73  5050.3 1865.67  5054.9 1865.67  5062.3 1869.30  5092.7 1880.55
  5104.2 1886.99  5123.1 1895.50  5133.2 1898.89  5143.4 1901.75  5194.0 1911.71
#Mann=3,-1,0
  4806.6     0.1       0  5002.5    0.05       0  5006.5     0.1       0
Bank Sta=5002.5,5006.5
Exp/Cntr=0.3,0.1

Type RM Length L Ch R = 1,3320,499,499,499
BEGIN DESCRIPTION:
Stream0321 6.0
END DESCRIPTION:
XS GIS Cut Line= 3
      1864774.98     13927725.00      1864946.14     13927721.33
      1865174.97     13928024.96
#Sta/Elev= 30
  4900.8 1894.88  4903.3 1894.88  4940.8 1879.37  4970.8 1863.19  4980.8 1854.18
  4998.8 1842.52  4999.1 1842.02  5002.8 1842.52  5040.8 1844.33  5138.9 1843.43
  5174.3 1847.32  5180.6 1850.39  5188.9 1851.40  5195.1 1854.92  5209.7 1857.81
  5216.0 1862.06  5224.3 1863.53  5230.5 1867.56  5238.8 1869.30  5245.1 1873.52
  5259.7 1877.15  5265.9 1882.94  5288.8 1890.38  5295.1 1894.15  5309.6 1897.89
  5315.9 1902.41  5338.8 1907.65  5365.9 1916.56  5415.8 1928.95  5452.2 1936.40
#Mann=3,-1,0
  4900.8     0.1       0  4998.8    0.05       0  5002.8     0.1       0
Bank Sta=4998.8,5002.8
Exp/Cntr=0.3,0.1

Type RM Length L Ch R = 1,2821,439,439,439
BEGIN DESCRIPTION:
Stream0321 5.0
END DESCRIPTION:
XS GIS Cut Line= 3
      1864425.02     13927825.02      1864725.00     13928125.00
      1864874.95     13928174.98
#Sta/Elev= 30
  4575.5 1924.25  4579.0 1924.25  4589.6 1919.69  4603.8 1915.25  4646.2 1899.04
  4674.5 1889.74  4702.8 1876.34  4716.9 1869.15  4745.2 1857.59  4787.6 1847.80
  4830.0 1839.90  4872.5 1835.02  4886.6 1834.19  5002.4 1834.47  5008.3 1833.49
  5008.5 1832.99  5012.0 1832.99  5012.3 1833.49  5020.8 1836.92  5041.9 1842.24
  5052.4 1849.66  5063.0 1852.72  5073.5 1856.69  5078.8 1862.94  5105.1 1871.62
  5115.7 1878.67  5136.8 1885.52  5147.3 1891.67  5155.2 1894.37  5157.8 1894.37
#Mann=3,-1,0
  4575.5     0.1       0  5008.3    0.05       0  5012.3     0.1       0
Bank Sta=5008.3,5012.3
Exp/Cntr=0.3,0.1

Type RM Length L Ch R = 1,2382,447,447,447
BEGIN DESCRIPTION:
Stream0321 4.0
END DESCRIPTION:
XS GIS Cut Line= 4
      1864047.87     13928372.74      1864370.16     13928408.74
      1864775.00     13928375.00      1865075.04     13928224.98
#Sta/Elev= 30
  4269.7 1903.88  4317.1 1900.27  4397.6 1888.92  4478.1 1870.41  4608.9 1851.32
  4696.7 1832.34  4739.3 1827.19  4795.8 1828.13  5051.3 1823.44  5051.6 1822.94
  5055.3 1823.44  5075.7 1824.28  5093.3 1828.62  5103.7 1834.36  5120.4 1838.92
  5126.0 1844.78  5142.8 1850.19  5148.4 1855.41  5165.2 1860.89  5170.7 1866.00
  5187.5 1872.85  5193.1 1878.49  5209.9 1884.30  5215.5 1890.26  5232.2 1896.66
  5237.8 1902.76  5254.6 1908.94  5282.5 1924.84  5313.3 1937.37  5335.7 1942.10
#Mann=5,-1,0
  4269.7     0.1       0  4795.8    0.07       0  5051.3    0.05       0
  5055.3    0.07       0  5093.3     0.1       0
Bank Sta=5051.3,5055.3
Exp/Cntr=0.3,0.1

Type RM Length L Ch R = 1,1935,429,429,429
BEGIN DESCRIPTION:
Stream0321 3.0
END DESCRIPTION:
XS GIS Cut Line= 3
      1864709.88     13929125.13      1865075.00     13928675.00
      1865324.97     13928425.03
#Sta/Elev= 30
  4420.3 1836.96  4452.4 1838.43  4530.8 1838.11  4732.6 1833.07  4751.3 1831.53
  4772.1 1827.78  4800.9 1825.16  4821.7 1821.55  4836.1 1820.33  4900.0 1817.77
  4935.5 1818.31  4994.7 1817.38  4994.9 1816.88  4998.7 1817.38  5002.0 1817.38
  5042.3 1818.29  5056.5 1820.00  5070.6 1823.22  5093.2 1832.67  5141.3 1859.71
  5155.5 1869.60  5197.9 1894.36  5226.2 1907.78  5240.3 1916.41  5296.9 1942.72
  5311.0 1949.98  5325.2 1959.66  5339.3 1966.20  5349.9 1969.13  5353.4 1969.13
#Mann=6,-1,0
  4420.3    0.07       0  4732.6     0.1       0  4994.7    0.05       0
  4998.7     0.1       0  5002.0    0.07       0  5093.2     0.1       0
Bank Sta=4994.7,4998.7
Exp/Cntr=0.3,0.1

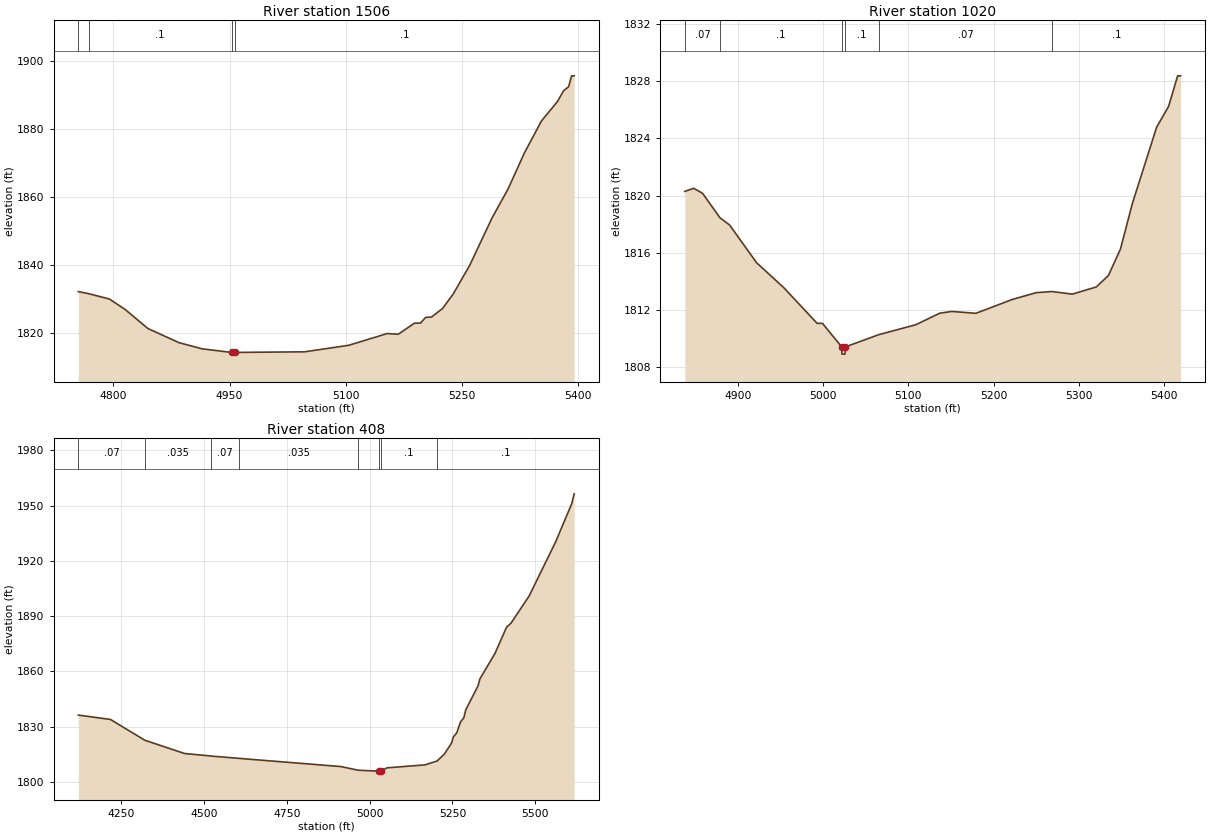
Type RM Length L Ch R = 1,1506,486,486,486
BEGIN DESCRIPTION:
Stream0321 2.0
END DESCRIPTION:
XS GIS Cut Line= 3
      1864975.05     13929025.00      1865225.00     13929025.00
      1865475.02     13928724.97
#Sta/Elev= 30
  4754.7 1832.13  4768.1 1831.51  4794.7 1829.95  4814.7 1826.95  4844.7 1821.24
  4884.7 1817.09  4914.7 1815.27  4952.7 1814.21  4952.9 1813.71  4956.7 1814.21
  5047.0 1814.39  5104.2 1816.32  5153.7 1819.77  5168.0 1819.57  5188.8 1822.81
  5196.7 1822.86  5203.2 1824.50  5211.0 1824.65  5225.3 1827.17  5239.0 1831.43
  5260.4 1839.92  5289.1 1853.81  5309.9 1862.38  5330.7 1872.85  5352.9 1882.36
  5373.7 1888.12  5381.5 1891.27  5388.0 1892.44  5391.9 1895.67  5395.2 1895.67
#Mann=4,-1,0
  4754.7    0.07       0  4768.1     0.1       0  4952.7    0.05       0
  4956.7     0.1       0
Bank Sta=4952.7,4956.7
Exp/Cntr=0.3,0.1

Type RM Length L Ch R = 1,1020,612,612,612
BEGIN DESCRIPTION:
Stream0321 1.0
END DESCRIPTION:
XS GIS Cut Line= 3
      1865075.04     13929425.01      1865225.00     13929475.00
      1865524.97     13929774.97
#Sta/Elev= 30
  4837.4 1820.29  4847.9 1820.51  4858.4 1820.15  4878.7 1818.45  4890.1 1817.94
  4921.7 1815.31  4953.3 1813.59  4992.8 1811.08  4999.0 1811.08  5021.8 1809.43
  5022.0 1808.93  5025.5 1808.93  5025.8 1809.43  5065.2 1810.29  5108.6 1810.98
  5136.9 1811.79  5151.0 1811.91  5179.3 1811.78  5221.7 1812.74  5250.0 1813.22
  5268.5 1813.30  5292.5 1813.12  5320.7 1813.62  5334.9 1814.42  5349.0 1816.26
  5363.2 1819.48  5391.5 1824.77  5405.6 1826.23  5416.2 1828.36  5419.7 1828.36
#Mann=6,-1,0
  4837.4    0.07       0  4878.7     0.1       0  5021.8    0.05       0
  5025.8     0.1       0  5065.2    0.07       0  5268.5     0.1       0
Bank Sta=5021.8,5025.8
Exp/Cntr=0.3,0.1

Type RM Length L Ch R = 1,408,0,0,0
BEGIN DESCRIPTION:
Stream0321 0.0
END DESCRIPTION:
XS GIS Cut Line= 4
      1864828.37     13929059.27      1864959.89     13929795.15
      1865017.55     13930048.60      1865441.40     13930296.14
#Sta/Elev= 30
  4119.6 1836.33  4216.8 1833.95  4320.3 1822.70  4440.3 1815.50  4521.3 1814.10
  4605.2 1812.84  4912.9 1808.40  4965.2 1806.42  5029.1 1805.88  5029.3 1805.38
  5033.1 1805.88  5052.3 1807.71  5167.1 1809.32  5203.8 1811.41  5225.8 1815.21
  5247.3 1821.09  5253.0 1824.56  5263.0 1826.65  5274.6 1832.67  5284.5 1834.86
  5290.2 1839.10  5327.4 1852.19  5333.2 1855.99  5378.9 1869.86  5413.6 1884.00
  5427.3 1886.25  5482.0 1900.99  5562.2 1930.39  5611.0 1951.20  5617.9 1956.35
#Mann=8,-1,0
  4119.6    0.07       0  4320.3   0.035       0  4521.3    0.07       0
  4605.2   0.035       0  4965.2     0.1       0  5029.1    0.05       0
  5033.1     0.1       0  5203.8     0.1       0
Bank Sta=5029.1,5033.1
Exp/Cntr=0.3,0.1

Chan Stop Cuts=-1