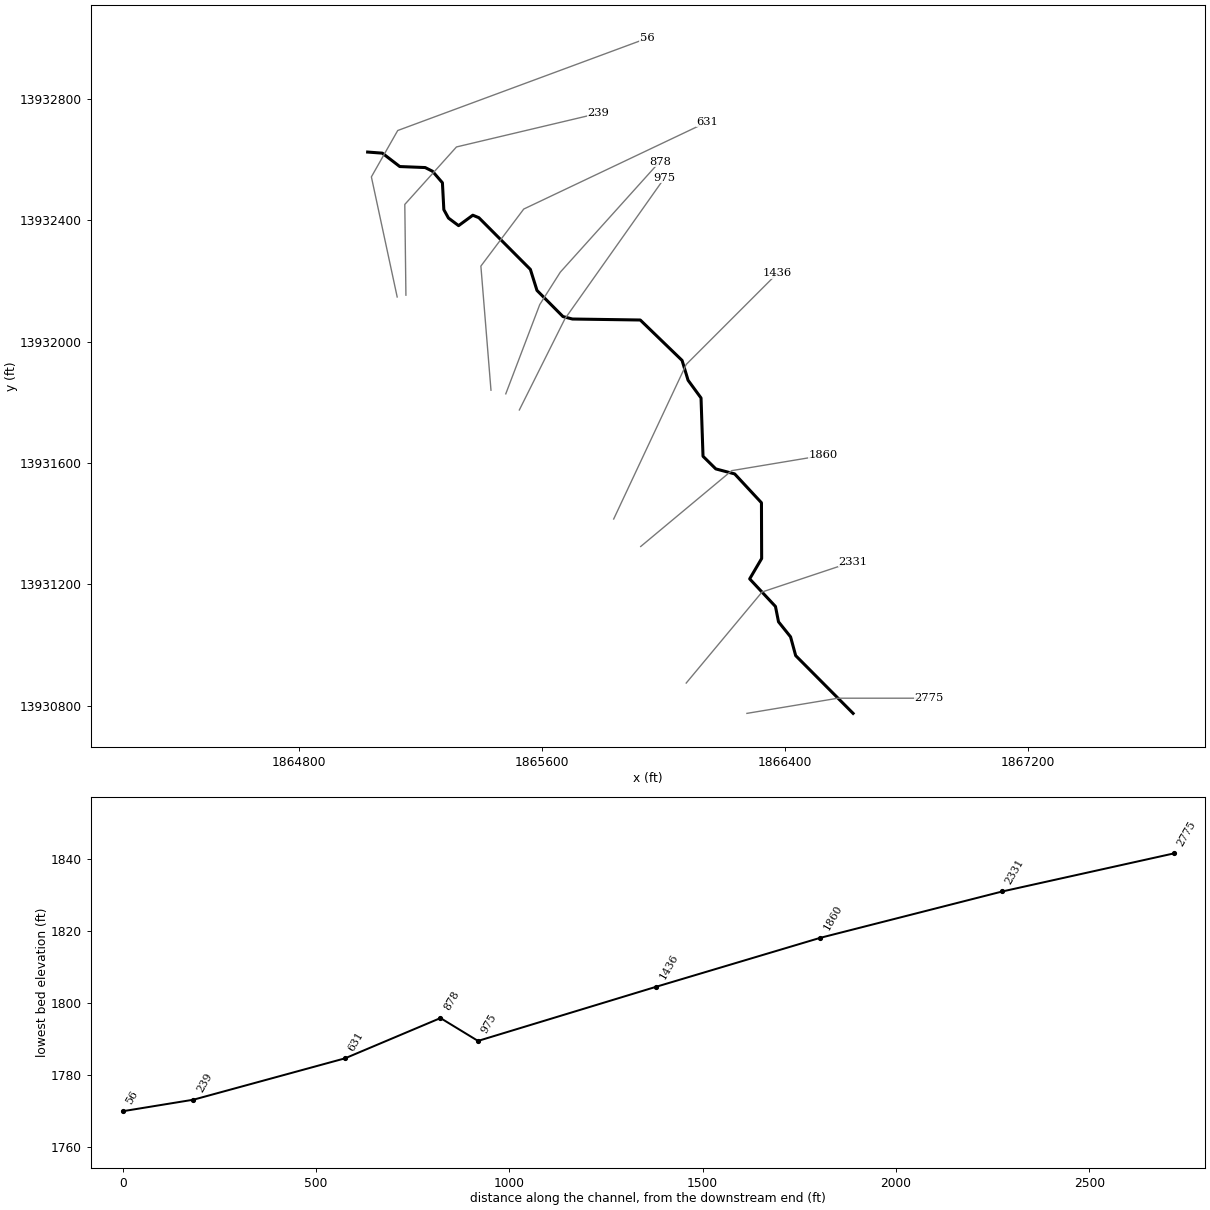
--- Stream0322.prj (project) ---

Proj Title=Stream0322 Base Level Engineering
Current Plan=p01
Default Exp/Contr=0.3,0.1
English Units
Geom File=g01
Flow File=f01
Plan File=p01
BEGIN DESCRIPTION:
Stream0322
END DESCRIPTION:

--- Stream0322.p01 (plan) ---

Plan Title=Multiple Run
Short Identifier=Multiple
Geom File=g01
Flow File=f01
Subcritical Flow
K Sum by GR= 0
Std Step Tol= 0.01
Critical Tol= 0.01
Num of Std Step Trials= 20
Max Error Tol= 0.3
Flow Tol Ratio= 0.001
Split Flow NTrial= 30
Split Flow Tol= 0.02
Split Flow Ratio= 0.02
Log Output Level= 0
Friction Slope Method= 1
Unsteady Friction Slope Method= 2
Unsteady Bridges Friction Slope Method= 1
Parabolic Critical Depth
Global Vel Dist=  1 , 1 , 1
Global Log Level= 0
CheckData=True
Encroach Param= -1, 0, 0, 0
BEGIN DESCRIPTION:
Multiple Run
END DESCRIPTION:

--- Stream0322.f01 (steady flow) ---

Flow Title=Multiple
Number of Profiles=7
Profile Names=10-year,25-year,50-year,1pct_min,100-year,1pct_plu,500-year
River Rch & RM= Stream0322,Reach-1,2775
     605    1003    1371     911    1817    3625    3142
Boundary for River Rch & Prof#=Stream0322,Reach-1,1
Up Type=0
Dn Type=3
Dn Slope=0.005
Boundary for River Rch & Prof#=Stream0322,Reach-1,2
Up Type=0
Dn Type=3
Dn Slope=0.005
Boundary for River Rch & Prof#=Stream0322,Reach-1,3
Up Type=0
Dn Type=3
Dn Slope=0.005
Boundary for River Rch & Prof#=Stream0322,Reach-1,4
Up Type=0
Dn Type=3
Dn Slope=0.005
Boundary for River Rch & Prof#=Stream0322,Reach-1,5
Up Type=0
Dn Type=3
Dn Slope=0.005
Boundary for River Rch & Prof#=Stream0322,Reach-1,6
Up Type=0
Dn Type=3
Dn Slope=0.005
Boundary for River Rch & Prof#=Stream0322,Reach-1,7
Up Type=0
Dn Type=3
Dn Slope=0.005

--- Stream0322.g01 (geometry) ---

Geom Title=Existing Conditions

River Reach=Stream0322,Reach-1
Reach XY= 30
      1866625.00     13930775.00      1866435.76     13930965.32
      1866418.90     13931027.19      1866379.19     13931076.74
      1866369.14     13931127.30      1866284.15     13931218.27
      1866323.61     13931285.43      1866322.95     13931469.16
      1866234.68     13931564.22      1866172.43     13931580.74
      1866130.36     13931622.30      1866123.80     13931814.50
      1866081.14     13931872.83      1866061.38     13931938.22
      1865923.54     13932071.46      1865699.87     13932074.70
      1865668.79     13932082.80      1865583.15     13932168.93
      1865561.37     13932238.21      1865391.66     13932408.61
      1865371.65     13932416.83      1865324.76     13932382.46
      1865291.46     13932407.39      1865276.17     13932435.16
      1865271.49     13932523.74      1865238.72     13932561.77
      1865214.69     13932573.91      1865130.93     13932577.23
      1865073.49     13932621.36      1865025.00     13932625.00

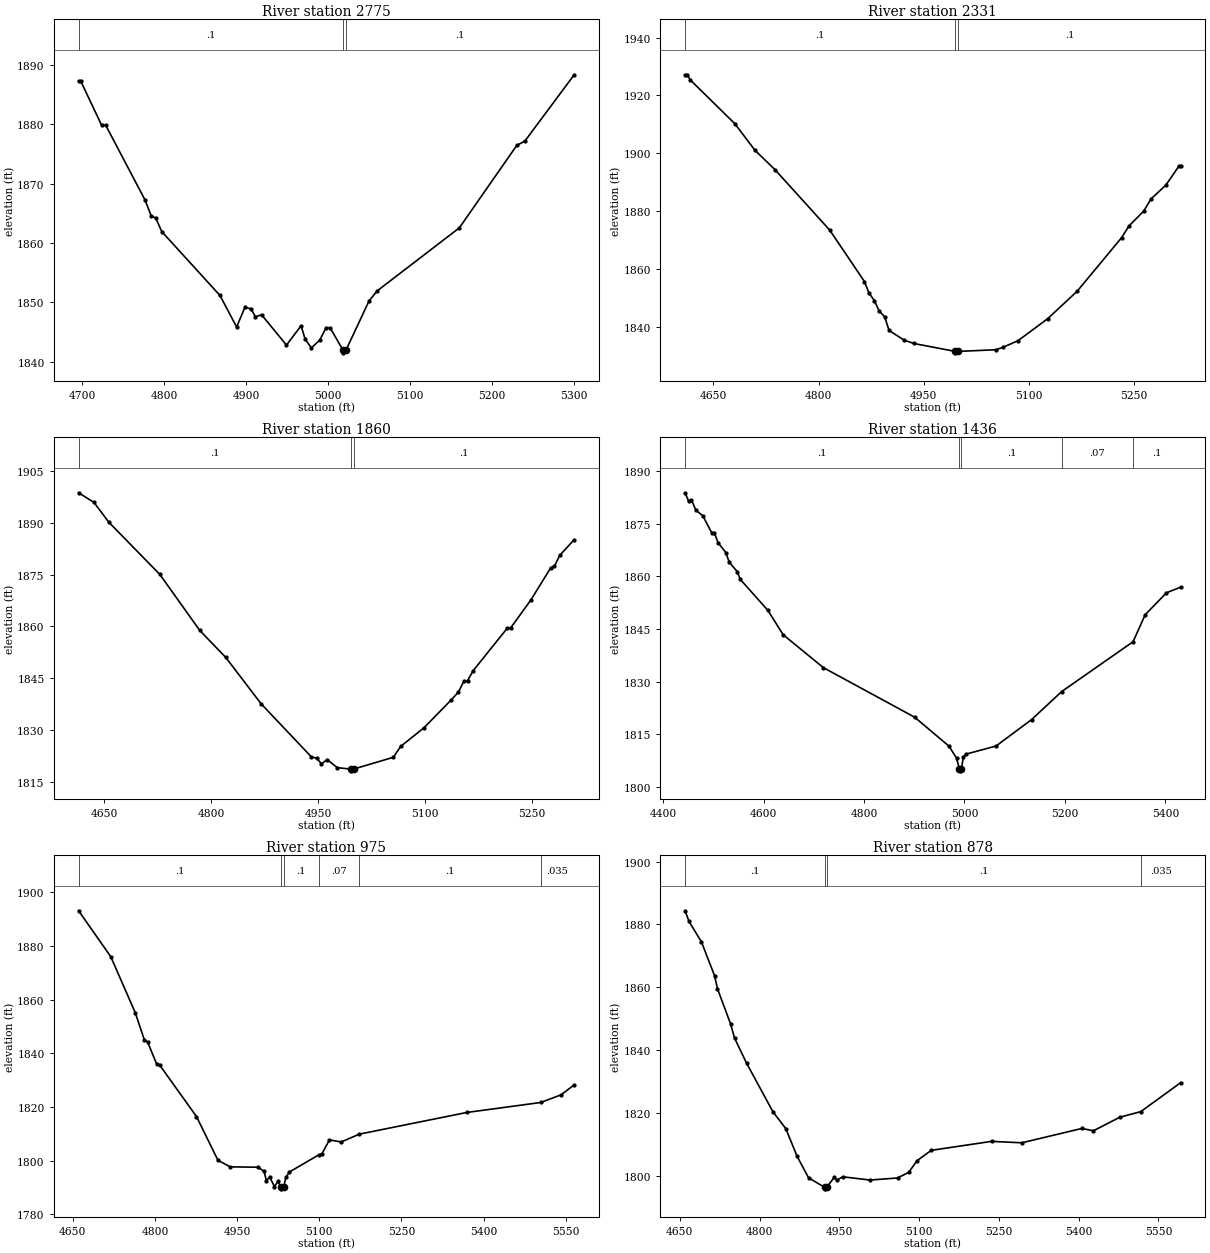
Type RM Length L Ch R = 1,2775,444,444,444
BEGIN DESCRIPTION:
Stream0322 5.0
END DESCRIPTION:
XS GIS Cut Line= 3
      1866275.02     13930775.00      1866575.00     13930825.00
      1866874.98     13930825.00
#Sta/Elev= 30
  4695.9 1887.30  4698.4 1887.30  4723.8 1879.88  4728.8 1879.87  4777.0 1867.22
  4784.6 1864.49  4789.7 1864.28  4797.3 1861.93  4868.2 1851.18  4888.5 1845.87
  4898.6 1849.18  4906.2 1848.92  4911.3 1847.59  4918.9 1847.93  4949.3 1842.82
  4967.1 1846.09  4972.1 1843.79  4979.7 1842.36  4989.9 1843.67  4997.5 1845.74
  5002.5 1845.74  5018.0 1842.02  5018.3 1841.52  5022.0 1842.02  5050.0 1850.28
  5060.0 1851.97  5160.0 1862.56  5230.0 1876.44  5240.0 1877.19  5300.0 1888.34
#Mann=3,-1,0
  4695.9     0.1       0  5018.0    0.05       0  5022.0     0.1       0
Bank Sta=5018,5022
Exp/Cntr=0.3,0.1

Type RM Length L Ch R = 1,2331,471,471,471
BEGIN DESCRIPTION:
Stream0322 4.0
END DESCRIPTION:
XS GIS Cut Line= 3
      1866074.97     13930874.97      1866325.00     13931175.00
      1866625.02     13931275.01
#Sta/Elev= 30
  4609.6 1927.16  4612.9 1927.16  4616.8 1925.43  4680.6 1910.22  4709.2 1901.06
  4737.9 1894.31  4816.0 1873.38  4865.4 1855.63  4871.9 1851.62  4879.7 1848.99
  4886.3 1845.43  4894.1 1843.48  4900.6 1838.69  4922.0 1835.35  4935.7 1834.20
  4994.9 1831.46  4995.1 1830.96  4998.9 1831.46  5052.9 1832.03  5063.4 1832.92
  5084.5 1835.17  5126.6 1842.74  5168.8 1852.27  5232.1 1870.78  5242.6 1874.84
  5263.7 1879.98  5274.2 1884.21  5295.3 1888.98  5313.7 1895.46  5316.4 1895.46
#Mann=3,-1,0
  4609.6     0.1       0  4994.9    0.05       0  4998.9     0.1       0
Bank Sta=4994.9,4998.9
Exp/Cntr=0.3,0.1

Type RM Length L Ch R = 1,1860,424,424,424
BEGIN DESCRIPTION:
Stream0322 3.0
END DESCRIPTION:
XS GIS Cut Line= 3
      1865925.02     13931325.02      1866225.00     13931575.00
      1866524.98     13931625.00
#Sta/Elev= 30
  4614.6 1898.81  4636.1 1896.01  4656.9 1890.27  4728.5 1875.09  4784.4 1858.85
  4820.9 1851.00  4870.4 1837.56  4940.6 1822.20  4948.5 1821.73  4955.0 1820.12
  4962.8 1821.37  4977.1 1819.03  4995.9 1818.60  4996.2 1818.10  4999.9 1818.60
  5055.8 1822.04  5065.9 1825.17  5098.9 1830.64  5136.9 1838.69  5147.0 1840.98
  5154.6 1844.12  5159.7 1844.21  5167.3 1847.09  5215.4 1859.50  5220.5 1859.68
  5248.4 1867.66  5276.3 1877.01  5281.3 1877.42  5288.9 1880.63  5309.2 1885.20
#Mann=3,-1,0
  4614.6     0.1       0  4995.9    0.05       0  4999.9     0.1       0
Bank Sta=4995.9,4999.9
Exp/Cntr=0.3,0.1

Type RM Length L Ch R = 1,1436,461,461,461
BEGIN DESCRIPTION:
Stream0322 2.0
END DESCRIPTION:
XS GIS Cut Line= 3
      1865835.96     13931415.60      1866075.00     13931925.00
      1866375.03     13932225.03
#Sta/Elev= 30
  4443.5 1883.80  4450.7 1881.35  4456.2 1881.76  4464.9 1878.86  4479.0 1877.20
  4496.3 1872.46  4501.8 1872.37  4509.1 1869.58  4524.7 1866.77  4531.2 1864.06
  4547.5 1861.31  4553.3 1859.13  4608.5 1850.26  4638.7 1843.35  4719.0 1833.95
  4900.8 1819.82  4969.2 1811.57  4984.1 1808.15  4990.0 1805.04  4990.3 1804.54
  4994.0 1805.04  4997.6 1808.51  5003.4 1809.32  5062.8 1811.61  5133.5 1819.13
  5193.6 1827.14  5335.8 1841.35  5359.8 1849.02  5402.2 1855.29  5430.5 1856.89
#Mann=5,-1,0
  4443.5     0.1       0  4990.0    0.05       0  4994.0     0.1       0
  5193.6    0.07       0  5335.8     0.1       0
Bank Sta=4990,4994
Exp/Cntr=0.3,0.1

Type RM Length L Ch R = 1,975,97,97,97
BEGIN DESCRIPTION:
Stream0322 1.0
END DESCRIPTION:
XS GIS Cut Line= 3
      1865524.99     13931774.99      1865675.00     13932075.00
      1866003.61     13932539.98
#Sta/Elev= 30
  4660.6 1893.07  4719.3 1875.97  4764.0 1855.10  4780.8 1844.88  4786.4 1844.28
  4803.2 1835.93  4808.8 1835.54  4875.8 1816.44  4915.0 1800.15  4937.3 1797.71
  4987.6 1797.57  4999.1 1796.10  5003.4 1792.57  5009.5 1793.93  5018.2 1790.32
  5024.3 1792.27  5030.8 1790.02  5031.0 1789.52  5034.8 1790.02  5039.1 1793.75
  5045.2 1795.76  5098.7 1802.13  5104.4 1802.41  5118.5 1807.74  5140.1 1806.98
  5173.2 1809.89  5369.0 1817.95  5504.5 1821.68  5541.4 1824.53  5565.4 1828.22
#Mann=6,-1,0
  4660.6     0.1       0  5030.8    0.05       0  5034.8     0.1       0
  5098.7    0.07       0  5173.2     0.1       0  5504.5   0.035       0
Bank Sta=5030.8,5034.8
Exp/Cntr=0.3,0.1

Type RM Length L Ch R = 1,878,247,247,247
BEGIN DESCRIPTION:
Stream0322 0.5
END DESCRIPTION:
XS GIS Cut Line= 4
      1865480.30     13931828.09      1865592.27     13932122.33
      1865659.98     13932229.11      1865988.13     13932593.72
#Sta/Elev= 30
  4660.0 1884.35  4667.4 1880.95  4690.7 1874.47  4715.5 1863.64  4720.9 1859.53
  4745.6 1848.31  4753.0 1843.82  4775.7 1835.82  4825.2 1820.37  4849.3 1815.04
  4870.7 1806.17  4892.1 1799.39  4922.2 1796.36  4922.4 1795.86  4926.2 1796.36
  4940.3 1799.47  4945.6 1798.63  4956.3 1799.70  5007.8 1798.66  5059.5 1799.32
  5080.6 1801.11  5095.9 1804.78  5122.8 1808.11  5236.4 1810.97  5293.2 1810.51
  5406.1 1815.08  5427.8 1814.33  5477.1 1818.63  5516.9 1820.44  5591.8 1829.64
#Mann=4,-1,0
  4660.0     0.1       0  4922.2    0.05       0  4926.2     0.1       0
  5516.9   0.035       0
Bank Sta=4922.2,4926.2
Exp/Cntr=0.3,0.1

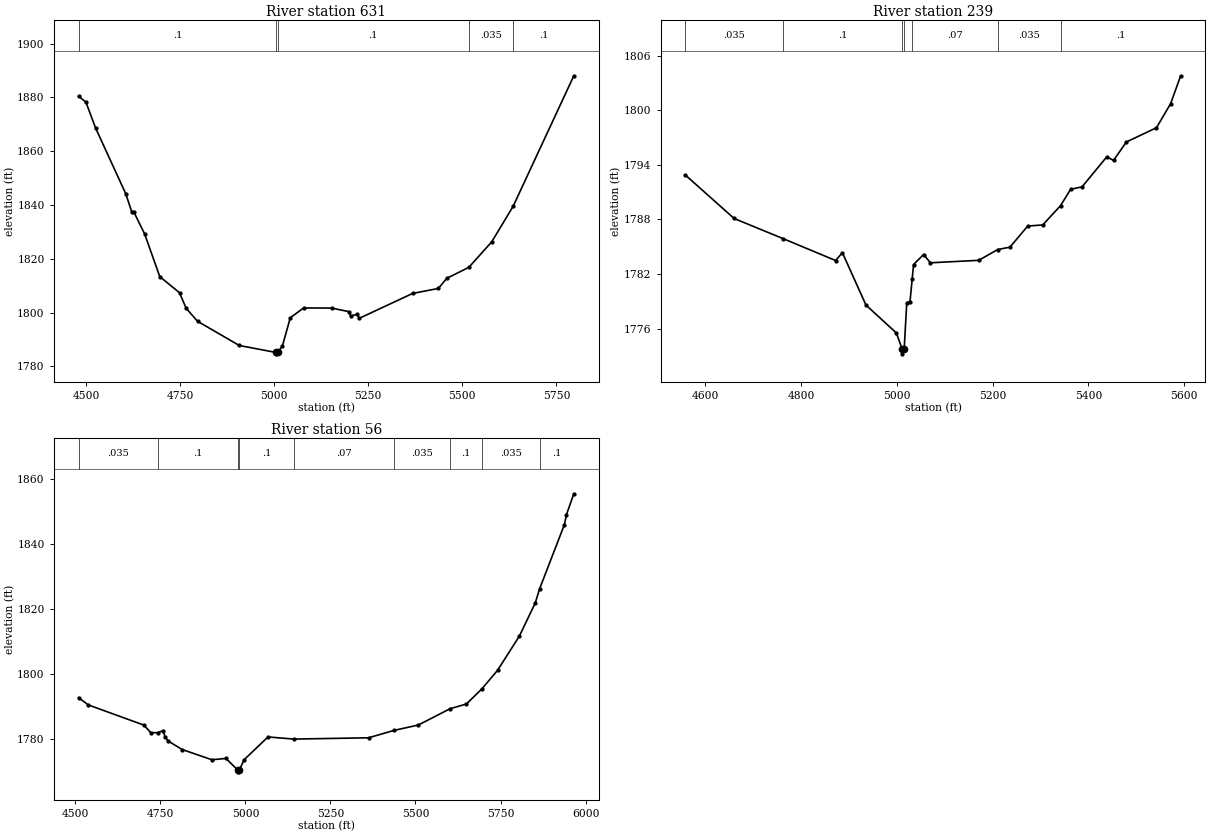
Type RM Length L Ch R = 1,631,392,392,392
BEGIN DESCRIPTION:
Stream0322 0.0
END DESCRIPTION:
XS GIS Cut Line= 4
      1865431.53     13931840.13      1865398.25     13932249.14
      1865539.48     13932437.12      1866144.93     13932724.57
#Sta/Elev= 30
  4480.6 1880.44  4500.0 1878.26  4525.6 1868.67  4605.9 1844.17  4621.9 1837.40
  4626.9 1837.53  4656.0 1829.27  4696.2 1813.40  4748.7 1807.40  4766.4 1801.61
  4796.5 1796.80  4907.5 1787.79  5005.5 1785.19  5005.8 1784.69  5009.5 1785.19
  5022.1 1787.63  5042.9 1798.08  5078.3 1801.74  5152.5 1801.71  5197.9 1800.40
  5203.4 1798.77  5220.6 1799.38  5226.2 1797.89  5368.1 1807.15  5436.3 1808.99
  5459.0 1812.78  5517.3 1816.83  5578.2 1826.33  5635.1 1839.55  5796.3 1888.05
#Mann=5,-1,0
  4480.6     0.1       0  5005.5    0.05       0  5009.5     0.1       0
  5517.3   0.035       0  5635.1     0.1       0
Bank Sta=5005.5,5009.5
Exp/Cntr=0.3,0.1

Type RM Length L Ch R = 1,239,183,183,183
BEGIN DESCRIPTION:
Stream0322 0.1
END DESCRIPTION:
XS GIS Cut Line= 4
      1865151.19     13932153.30      1865147.50     13932452.38
      1865317.77     13932641.81      1865785.33     13932752.55
#Sta/Elev= 30
  4558.5 1792.87  4660.2 1788.10  4762.8 1785.88  4872.1 1783.48  4886.3 1784.34
  4935.6 1778.58  4999.1 1775.51  5011.3 1773.72  5011.6 1773.22  5015.3 1773.72
  5020.8 1778.85  5027.5 1778.95  5032.0 1781.40  5035.0 1783.04  5055.9 1784.14
  5070.2 1783.23  5171.1 1783.50  5210.7 1784.69  5236.3 1784.95  5273.4 1787.27
  5304.7 1787.39  5341.9 1789.51  5363.0 1791.31  5386.9 1791.58  5438.3 1794.87
  5452.7 1794.49  5479.4 1796.51  5542.3 1798.08  5571.9 1800.73  5592.8 1803.79
#Mann=7,-1,0
  4558.5   0.035       0  4762.8     0.1       0  5011.3    0.05       0
  5015.3     0.1       0  5032.0    0.07       0  5210.7   0.035       0
  5341.9     0.1       0
Bank Sta=5011.3,5015.3
Exp/Cntr=0.3,0.1

Type RM Length L Ch R = 1,56,0,0,0
BEGIN DESCRIPTION:
Stream0322 0.2
END DESCRIPTION:
XS GIS Cut Line= 4
      1865122.40     13932147.40      1865037.34     13932543.19
      1865124.15     13932695.97      1865945.30     13932999.78
#Sta/Elev= 30
  4509.5 1792.86  4537.7 1790.62  4701.4 1784.40  4721.8 1782.07  4742.4 1782.06
  4758.3 1782.72  4763.4 1780.72  4773.0 1779.49  4813.9 1776.89  4901.3 1773.74
  4942.6 1774.14  4978.1 1770.52  4978.3 1770.02  4982.1 1770.52  4995.9 1773.73
  5066.5 1780.76  5141.8 1780.10  5361.9 1780.49  5436.3 1782.75  5508.6 1784.43
  5601.9 1789.45  5650.0 1790.90  5695.7 1795.60  5741.4 1801.26  5805.3 1811.75
  5852.1 1821.96  5864.9 1826.31  5938.0 1846.11  5944.0 1849.19  5965.6 1855.57
#Mann=9,-1,0
  4509.5   0.035       0  4742.4     0.1       0  4978.1    0.05       0
  4982.1     0.1       0  5141.8    0.07       0  5436.3   0.035       0
  5601.9     0.1       0  5695.7   0.035       0  5864.9     0.1       0
Bank Sta=4978.1,4982.1
Exp/Cntr=0.3,0.1

Chan Stop Cuts=-1