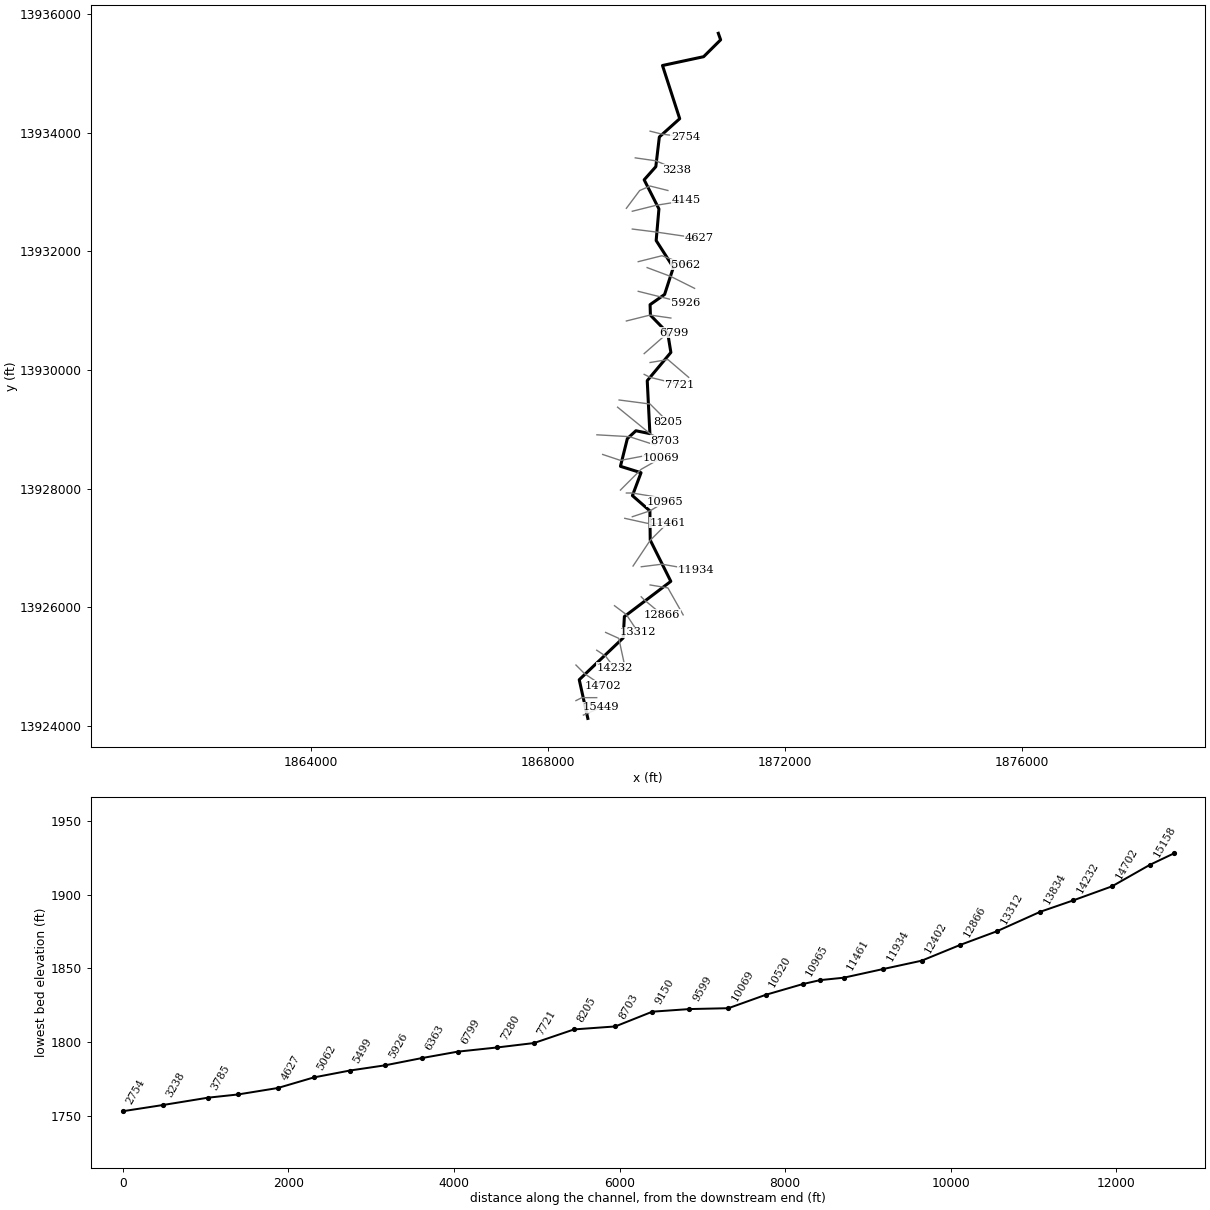
--- Stream0323.prj (project) ---

Proj Title=Stream0323 Base Level Engineering
Current Plan=p01
Default Exp/Contr=0.3,0.1
English Units
Geom File=g01
Flow File=f01
Plan File=p01
BEGIN DESCRIPTION:
Stream0323
END DESCRIPTION:

--- Stream0323.p01 (plan) ---

Plan Title=Multiple Run
Short Identifier=Multiple
Geom File=g01
Flow File=f01
Subcritical Flow
K Sum by GR= 0
Std Step Tol= 0.01
Critical Tol= 0.01
Num of Std Step Trials= 20
Max Error Tol= 0.3
Flow Tol Ratio= 0.001
Split Flow NTrial= 30
Split Flow Tol= 0.02
Split Flow Ratio= 0.02
Log Output Level= 0
Friction Slope Method= 1
Unsteady Friction Slope Method= 2
Unsteady Bridges Friction Slope Method= 1
Parabolic Critical Depth
Global Vel Dist=  1 , 1 , 1
Global Log Level= 0
CheckData=True
Encroach Param= -1, 0, 0, 0
BEGIN DESCRIPTION:
Multiple Run
END DESCRIPTION:

--- Stream0323.f01 (steady flow) ---

Flow Title=Multiple
Number of Profiles=7
Profile Names=10-year,25-year,50-year,1pct_min,100-year,1pct_plu,500-year
River Rch & RM= Stream0323,Reach-1,15449
    1028    1767    2478    1684    3359    6702    6089
River Rch & RM= Stream0323,Reach-1,11176
    1348    2353    3334    2285    4559    9097    8420
River Rch & RM= Stream0323,Reach-1,9599
    2203    3924    5631    3899    7779   15521   14676
Boundary for River Rch & Prof#=Stream0323,Reach-1,1
Up Type=0
Dn Type=3
Dn Slope=0.005
Boundary for River Rch & Prof#=Stream0323,Reach-1,2
Up Type=0
Dn Type=3
Dn Slope=0.005
Boundary for River Rch & Prof#=Stream0323,Reach-1,3
Up Type=0
Dn Type=3
Dn Slope=0.005
Boundary for River Rch & Prof#=Stream0323,Reach-1,4
Up Type=0
Dn Type=3
Dn Slope=0.005
Boundary for River Rch & Prof#=Stream0323,Reach-1,5
Up Type=0
Dn Type=3
Dn Slope=0.005
Boundary for River Rch & Prof#=Stream0323,Reach-1,6
Up Type=0
Dn Type=3
Dn Slope=0.005
Boundary for River Rch & Prof#=Stream0323,Reach-1,7
Up Type=0
Dn Type=3
Dn Slope=0.005

--- Stream0323.g01 (geometry) ---

Geom Title=Existing Conditions

River Reach=Stream0323,Reach-1
Reach XY= 30
      1868675.00     13924125.00      1868530.46     13924777.45
      1869271.97     13925483.01      1869291.20     13925841.71
      1870074.25     13926435.68      1869727.24     13927130.93
      1869721.47     13927623.55      1869427.05     13927880.86
      1869572.16     13928266.99      1869225.00     13928375.00
      1869341.43     13928841.77      1869485.64     13928974.45
      1869721.55     13928926.19      1869676.80     13929818.89
      1870075.11     13930295.09      1870021.46     13930623.54
      1869730.45     13930922.53      1869724.66     13931100.22
      1869969.55     13931272.53      1870117.21     13931728.42
      1869827.26     13932180.94      1869873.80     13932714.50
      1869624.96     13933205.02      1869821.46     13933426.46
      1869880.84     13933927.29      1870223.96     13934235.43
      1869934.01     13935132.02      1870627.43     13935280.52
      1870914.01     13935564.96      1870875.00     13935675.00

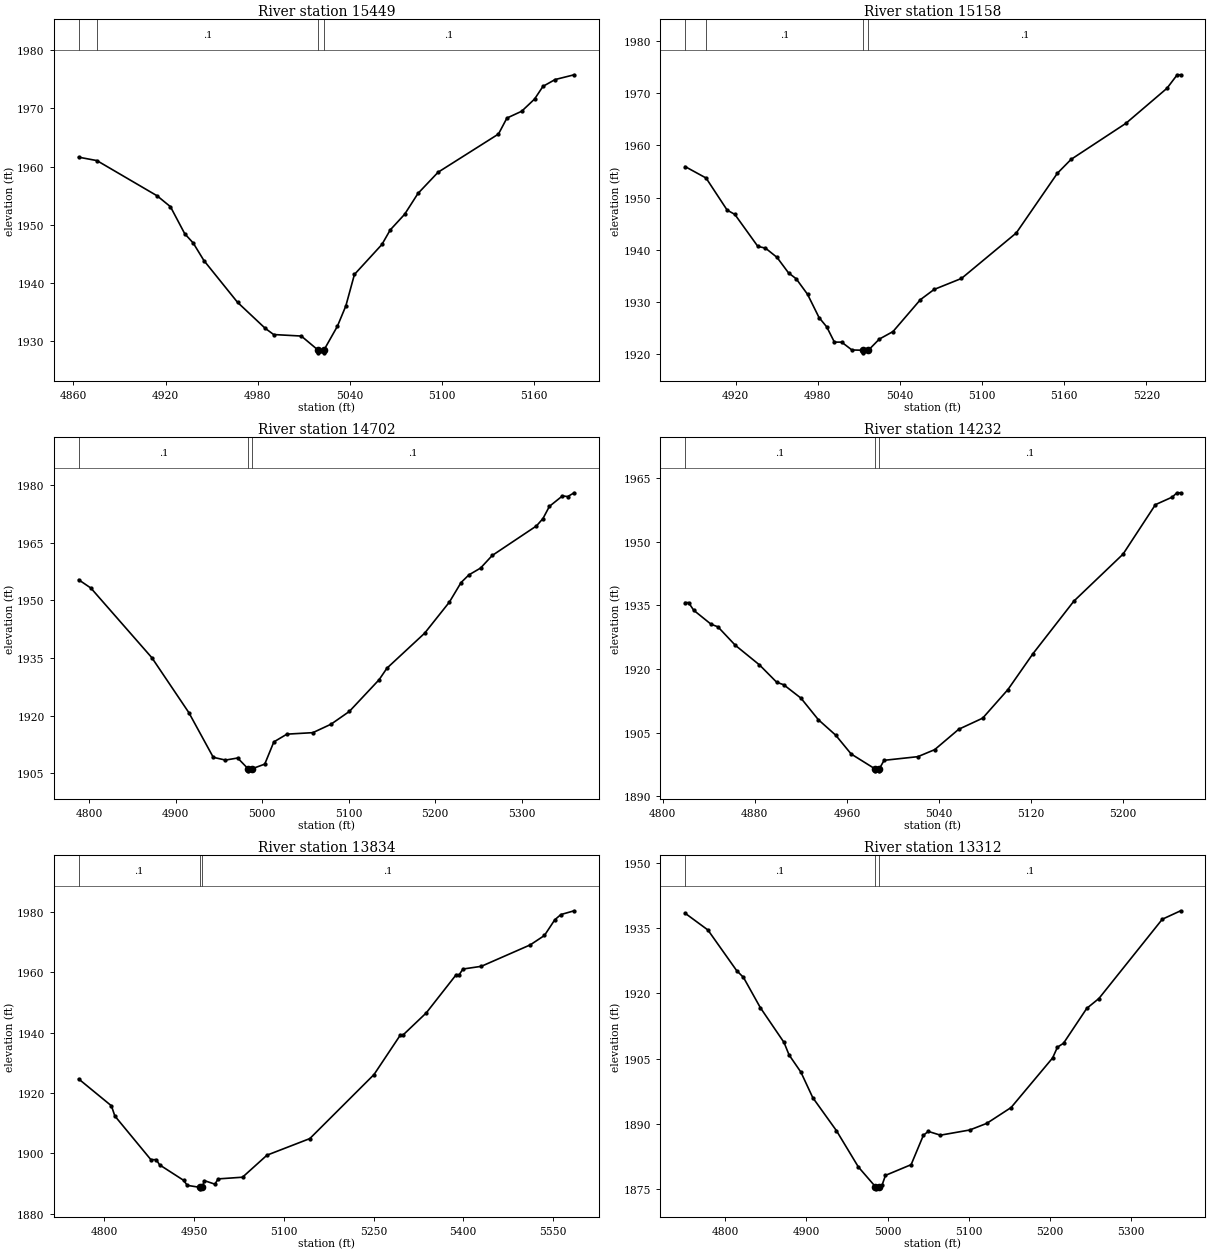
Type RM Length L Ch R = 1,15449,291,291,291
BEGIN DESCRIPTION:
Stream0323 32.0
END DESCRIPTION:
XS GIS Cut Line= 2
      1868600.14     13924181.04      1868896.36     13924309.07
#Sta/Elev= 30
  4863.4 1961.61  4875.3 1961.02  4914.5 1954.96  4923.2 1953.08  4932.5 1948.43
  4938.0 1946.84  4945.0 1943.81  4966.9 1936.62  4984.9 1932.15  4990.4 1931.08
  5008.4 1930.82  5019.2 1928.43  5019.5 1927.93  5023.0 1927.93  5023.2 1928.43
  5031.9 1932.50  5037.4 1936.00  5043.0 1941.42  5060.9 1946.58  5066.3 1949.08
  5075.7 1951.78  5084.4 1955.37  5097.5 1959.02  5136.8 1965.59  5142.3 1968.34
  5151.9 1969.51  5160.3 1971.61  5165.8 1973.80  5173.7 1974.97  5186.1 1975.79
#Mann=4,-1,0
  4863.4    0.07       0  4875.3     0.1       0  5019.2    0.05       0
  5023.2     0.1       0
Bank Sta=5019.2,5023.2
Exp/Cntr=0.3,0.1

Type RM Length L Ch R = 1,15158,456,456,456
BEGIN DESCRIPTION:
Stream0323 31.0
END DESCRIPTION:
XS GIS Cut Line= 3
      1868475.00     13924425.00      1868575.00     13924475.00
      1868825.00     13924475.00
#Sta/Elev= 30
  4883.2 1955.95  4898.5 1953.75  4913.9 1947.58  4919.5 1946.76  4936.3 1940.61
  4941.9 1940.27  4950.3 1938.50  4958.7 1935.52  4964.3 1934.39  4972.6 1931.40
  4981.0 1926.93  4986.6 1925.14  4992.2 1922.21  4997.5 1922.21  5005.0 1920.70
  5013.0 1920.65  5013.2 1920.15  5017.0 1920.65  5025.0 1922.79  5035.0 1924.24
  5055.0 1930.37  5065.0 1932.33  5085.0 1934.45  5125.0 1943.19  5155.0 1954.66
  5165.0 1957.33  5205.0 1964.25  5235.0 1970.99  5242.5 1973.59  5245.0 1973.59
#Mann=4,-1,0
  4883.2    0.07       0  4898.5     0.1       0  5013.0    0.05       0
  5017.0     0.1       0
Bank Sta=5013,5017
Exp/Cntr=0.3,0.1

Type RM Length L Ch R = 1,14702,470,470,470
BEGIN DESCRIPTION:
Stream0323 30.0
END DESCRIPTION:
XS GIS Cut Line= 3
      1868475.01     13925024.99      1868625.00     13924875.00
      1868925.02     13924674.99
#Sta/Elev= 30
  4787.9 1955.34  4802.0 1953.19  4872.7 1935.00  4915.2 1920.78  4943.5 1909.12
  4957.6 1908.40  4971.7 1908.94  4983.9 1906.10  4984.1 1905.60  4987.9 1906.10
  5003.0 1907.35  5013.5 1913.13  5028.6 1915.15  5058.6 1915.54  5079.6 1917.74
  5100.7 1921.05  5135.2 1929.33  5144.2 1932.32  5187.8 1941.43  5216.4 1949.53
  5229.9 1954.62  5238.9 1956.60  5252.4 1958.38  5265.9 1961.66  5317.0 1969.35
  5324.5 1971.26  5332.0 1974.45  5347.1 1977.17  5353.1 1976.99  5360.6 1977.98
#Mann=3,-1,0
  4787.9     0.1       0  4983.9    0.05       0  4987.9     0.1       0
Bank Sta=4983.9,4987.9
Exp/Cntr=0.3,0.1

Type RM Length L Ch R = 1,14232,398,398,398
BEGIN DESCRIPTION:
Stream0323 29.0
END DESCRIPTION:
XS GIS Cut Line= 3
      1868825.01     13925274.99      1868975.00     13925175.00
      1869125.02     13924974.97
#Sta/Elev= 30
  4819.5 1935.69  4822.5 1935.69  4827.0 1933.87  4842.0 1930.59  4848.0 1929.97
  4863.1 1925.62  4884.1 1920.99  4899.1 1916.89  4905.1 1916.32  4920.1 1913.16
  4935.2 1908.08  4950.2 1904.45  4963.7 1899.99  4984.2 1896.52  4984.5 1896.02
  4988.0 1896.02  4988.2 1896.52  4992.3 1898.50  5021.6 1899.36  5036.2 1901.01
  5057.1 1905.82  5077.9 1908.44  5099.8 1915.17  5121.6 1923.65  5157.1 1936.03
  5199.8 1947.11  5227.9 1958.77  5242.5 1960.55  5246.6 1961.57  5249.8 1961.57
#Mann=3,-1,0
  4819.5     0.1       0  4984.2    0.05       0  4988.2     0.1       0
Bank Sta=4984.2,4988.2
Exp/Cntr=0.3,0.1

Type RM Length L Ch R = 1,13834,522,522,522
BEGIN DESCRIPTION:
Stream0323 28.0
END DESCRIPTION:
XS GIS Cut Line= 3
      1868975.03     13925574.99      1869196.98     13925474.60
      1869320.97     13924903.30
#Sta/Elev= 30
  4757.1 1924.68  4811.9 1915.78  4817.6 1912.42  4877.8 1897.96  4886.9 1897.95
  4892.4 1896.23  4932.7 1891.09  4938.6 1889.44  4959.7 1888.79  4960.0 1888.29
  4963.7 1888.79  4967.2 1891.01  4984.8 1889.84  4990.3 1891.58  5031.0 1892.14
  5071.9 1899.44  5143.5 1904.93  5250.8 1926.14  5294.9 1939.25  5300.0 1939.36
  5338.0 1946.53  5388.1 1959.19  5393.2 1959.21  5399.4 1961.07  5430.1 1961.97
  5511.9 1969.07  5535.6 1972.18  5552.9 1977.38  5563.1 1979.11  5585.3 1980.36
#Mann=3,-1,0
  4757.1     0.1       0  4959.7    0.05       0  4963.7     0.1       0
Bank Sta=4959.7,4963.7
Exp/Cntr=0.3,0.1

Type RM Length L Ch R = 1,13312,446,446,446
BEGIN DESCRIPTION:
Stream0323 27.0
END DESCRIPTION:
XS GIS Cut Line= 3
      1869125.00     13926025.00      1869325.00     13925875.00
      1869525.02     13925574.97
#Sta/Elev= 30
  4750.5 1938.39  4778.6 1934.54  4814.0 1925.22  4822.4 1923.66  4843.2 1916.71
  4872.4 1908.72  4878.6 1905.86  4893.2 1901.90  4907.8 1896.05  4937.0 1888.46
  4964.0 1880.13  4985.0 1875.61  4985.2 1875.11  4989.0 1875.61  4993.2 1875.97
  4997.4 1878.20  5029.0 1880.66  5044.1 1887.40  5050.1 1888.30  5065.1 1887.43
  5101.2 1888.62  5122.2 1890.14  5152.2 1893.78  5203.3 1905.15  5209.3 1907.63
  5216.8 1908.54  5245.4 1916.54  5260.4 1918.81  5338.5 1937.01  5361.1 1938.95
#Mann=3,-1,0
  4750.5     0.1       0  4985.0    0.05       0  4989.0     0.1       0
Bank Sta=4985,4989
Exp/Cntr=0.3,0.1

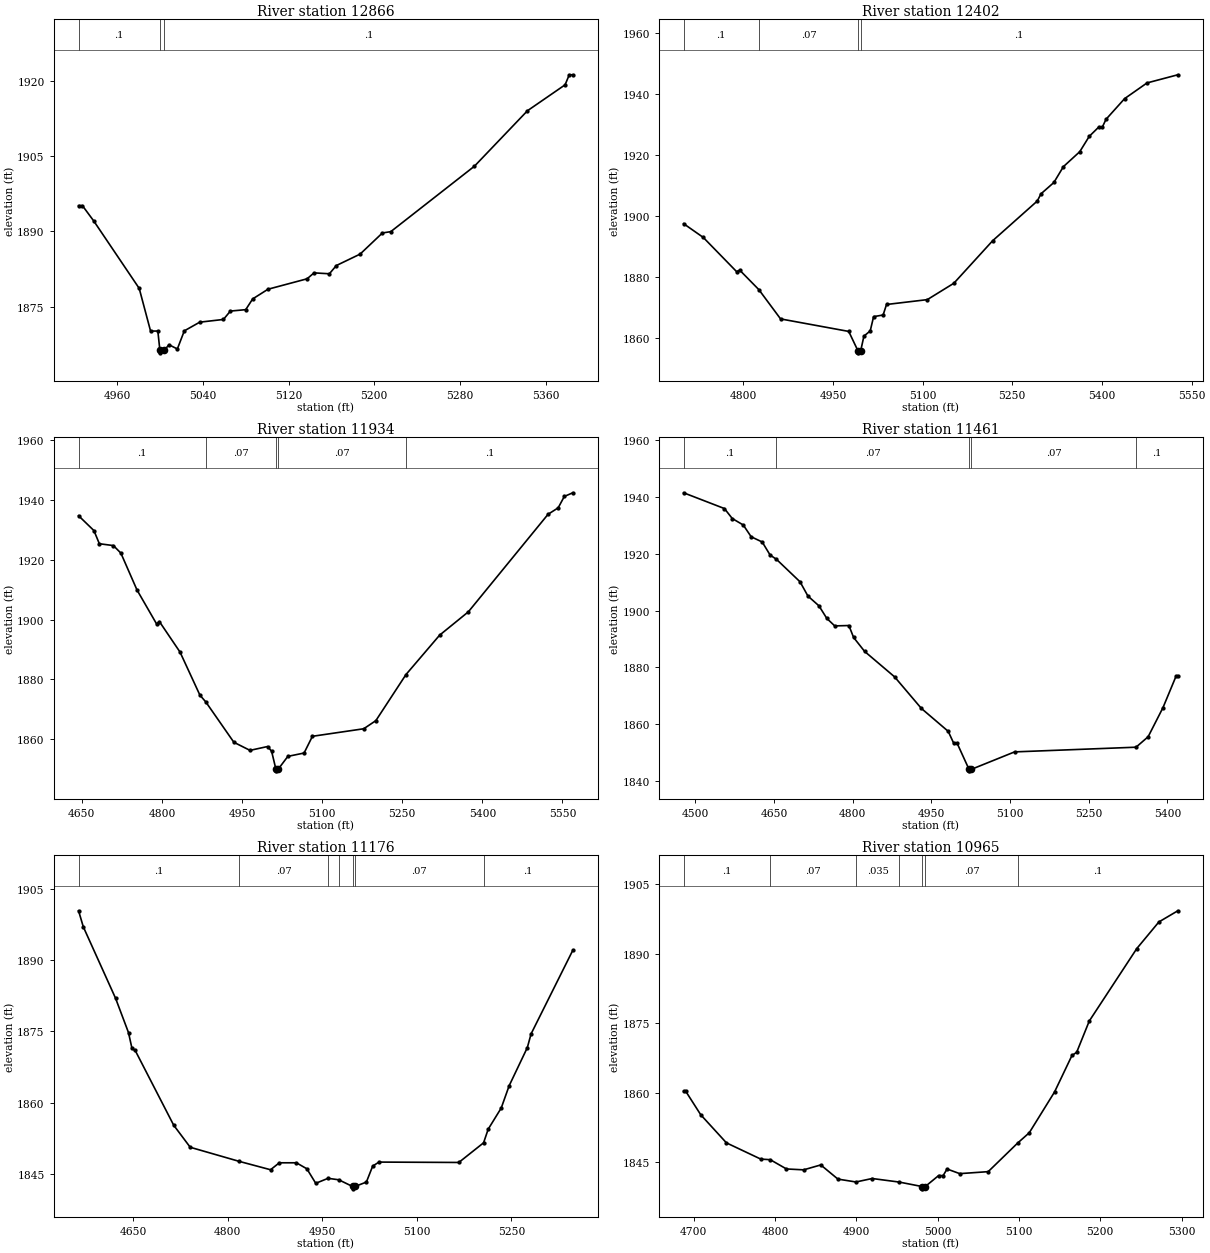
Type RM Length L Ch R = 1,12866,464,464,464
BEGIN DESCRIPTION:
Stream0323 26.0
END DESCRIPTION:
XS GIS Cut Line= 3
      1869574.97     13926175.03      1869625.00     13926125.00
      1869925.02     13925874.98
#Sta/Elev= 30
  4924.0 1895.10  4927.6 1895.10  4938.2 1892.04  4980.6 1878.62  4991.2 1870.12
  4998.0 1870.12  4999.9 1866.28  5000.2 1865.78  5003.9 1866.28  5008.4 1867.39
  5016.2 1866.55  5022.7 1870.16  5037.1 1871.89  5059.2 1872.43  5065.7 1874.10
  5080.0 1874.38  5086.5 1876.52  5100.8 1878.45  5137.3 1880.53  5143.8 1881.71
  5158.1 1881.53  5164.6 1883.17  5186.8 1885.45  5207.6 1889.66  5215.4 1889.92
  5293.5 1902.96  5343.0 1914.01  5378.1 1919.17  5382.0 1921.17  5385.3 1921.17
#Mann=3,-1,0
  4924.0     0.1       0  4999.9    0.05       0  5003.9     0.1       0
Bank Sta=4999.9,5003.9
Exp/Cntr=0.3,0.1

Type RM Length L Ch R = 1,12402,468,468,468
BEGIN DESCRIPTION:
Stream0323 25.0
END DESCRIPTION:
XS GIS Cut Line= 3
      1869725.01     13926375.00      1870025.00     13926325.00
      1870282.70     13925870.50
#Sta/Elev= 30
  4700.3 1897.46  4733.2 1892.95  4789.0 1881.73  4794.1 1882.24  4826.2 1875.83
  4862.5 1866.24  4976.5 1862.14  4992.3 1855.62  4992.5 1855.12  4996.3 1855.62
  5001.9 1860.61  5012.4 1862.29  5018.1 1866.99  5034.0 1867.52  5039.7 1870.97
  5107.9 1872.56  5152.3 1877.93  5217.2 1891.87  5291.8 1904.88  5298.0 1907.24
  5319.6 1910.96  5335.5 1916.15  5362.9 1921.06  5378.8 1926.10  5394.7 1929.14
  5400.4 1929.03  5406.8 1931.67  5437.9 1938.45  5475.4 1943.60  5526.9 1946.27
#Mann=4,-1,0
  4700.3     0.1       0  4826.2    0.07       0  4992.3    0.05       0
  4996.3     0.1       0
Bank Sta=4992.3,4996.3
Exp/Cntr=0.3,0.1

Type RM Length L Ch R = 1,11934,473,473,473
BEGIN DESCRIPTION:
Stream0323 24.0
END DESCRIPTION:
XS GIS Cut Line= 3
      1869576.40     13926681.84      1869925.00     13926725.00
      1870490.62     13926625.90
#Sta/Elev= 30
  4643.9 1934.79  4672.7 1929.81  4682.8 1925.42  4709.1 1924.80  4723.1 1922.29
  4753.3 1909.95  4790.1 1898.55  4795.2 1899.39  4833.9 1889.16  4871.1 1874.76
  4882.2 1872.47  4934.7 1858.98  4964.9 1856.27  4997.7 1857.55  5005.3 1856.02
  5013.5 1849.92  5013.7 1849.42  5017.5 1849.92  5035.8 1854.26  5066.2 1855.38
  5081.8 1860.98  5177.9 1863.50  5200.6 1866.22  5257.0 1881.64  5320.0 1894.82
  5373.8 1902.63  5523.1 1935.28  5542.0 1937.43  5553.5 1941.24  5569.4 1942.47
#Mann=5,-1,0
  4643.9     0.1       0  4882.2    0.07       0  5013.5    0.05       0
  5017.5    0.07       0  5257.0     0.1       0
Bank Sta=5013.5,5017.5
Exp/Cntr=0.3,0.1

Type RM Length L Ch R = 1,11461,285,285,285
BEGIN DESCRIPTION:
Stream0323 23.0
END DESCRIPTION:
XS GIS Cut Line= 3
      1869437.61     13926694.16      1869725.00     13927125.00
      1870025.03     13927425.03
#Sta/Elev= 30
  4477.6 1941.46  4555.4 1935.91  4570.4 1932.40  4591.4 1930.11  4606.4 1925.98
  4627.5 1924.13  4642.5 1919.55  4654.7 1918.03  4699.6 1910.12  4714.6 1905.11
  4735.6 1901.67  4750.6 1897.25  4765.7 1894.60  4792.7 1894.73  4801.7 1890.53
  4822.7 1885.62  4879.8 1876.67  4930.9 1865.55  4982.0 1857.50  4992.5 1853.31
  4999.0 1853.31  5021.8 1844.08  5022.0 1843.58  5025.8 1844.08  5108.6 1850.25
  5340.1 1851.90  5363.2 1855.58  5391.5 1865.83  5416.2 1876.81  5419.8 1876.81
#Mann=5,-1,0
  4477.6     0.1       0  4654.7    0.07       0  5021.8    0.05       0
  5025.8    0.07       0  5340.1     0.1       0
Bank Sta=5021.8,5025.8
Exp/Cntr=0.3,0.1

Type RM Length L Ch R = 1,11176,211,211,211
BEGIN DESCRIPTION:
Stream0323 22.1
END DESCRIPTION:
XS GIS Cut Line= 4
      1869297.63     13927498.31      1869675.26     13927414.97
      1869847.13     13927408.46      1870064.57     13927467.05
#Sta/Elev= 30
  4563.5 1900.34  4571.0 1896.97  4622.2 1881.96  4642.7 1874.75  4648.2 1871.44
  4653.3 1871.01  4714.4 1855.30  4740.6 1850.67  4818.0 1847.72  4868.0 1845.95
  4881.9 1847.41  4909.0 1847.41  4925.6 1846.15  4939.7 1843.10  4959.2 1844.15
  4976.2 1843.84  4998.0 1842.44  4998.2 1841.94  5002.0 1842.44  5020.0 1843.36
  5030.0 1846.72  5040.0 1847.56  5166.6 1847.48  5205.9 1851.61  5213.2 1854.47
  5233.9 1858.92  5246.4 1863.58  5275.3 1871.61  5281.2 1874.48  5347.4 1892.04
#Mann=7,-1,0
  4563.5     0.1       0  4818.0    0.07       0  4959.2   0.035       0
  4976.2    0.07       0  4998.0    0.05       0  5002.0    0.07       0
  5205.9     0.1       0
Bank Sta=4998,5002
Exp/Cntr=0.3,0.1

Type RM Length L Ch R = 1,10965,445,445,445
BEGIN DESCRIPTION:
Stream0323 22.0
END DESCRIPTION:
XS GIS Cut Line= 3
      1869424.98     13927524.99      1869725.00     13927625.00
      1869975.01     13927775.00
#Sta/Elev= 30
  4687.6 1860.27  4690.3 1860.27  4708.7 1855.21  4740.3 1849.15  4782.5 1845.65
  4794.2 1845.52  4814.1 1843.52  4835.2 1843.33  4856.3 1844.39  4877.4 1841.33
  4899.6 1840.71  4919.5 1841.46  4952.8 1840.69  4980.8 1839.73  4981.0 1839.23
  4984.8 1839.73  5001.2 1842.09  5006.8 1842.09  5011.6 1843.51  5027.2 1842.51
  5062.2 1842.94  5098.4 1849.11  5112.7 1851.33  5143.8 1860.14  5165.2 1868.01
  5171.0 1868.70  5186.5 1875.45  5244.9 1891.08  5272.1 1896.83  5295.4 1899.24
#Mann=7,-1,0
  4687.6     0.1       0  4794.2    0.07       0  4899.6   0.035       0
  4952.8    0.07       0  4980.8    0.05       0  4984.8    0.07       0
  5098.4     0.1       0
Bank Sta=4980.8,4984.8
Exp/Cntr=0.3,0.1

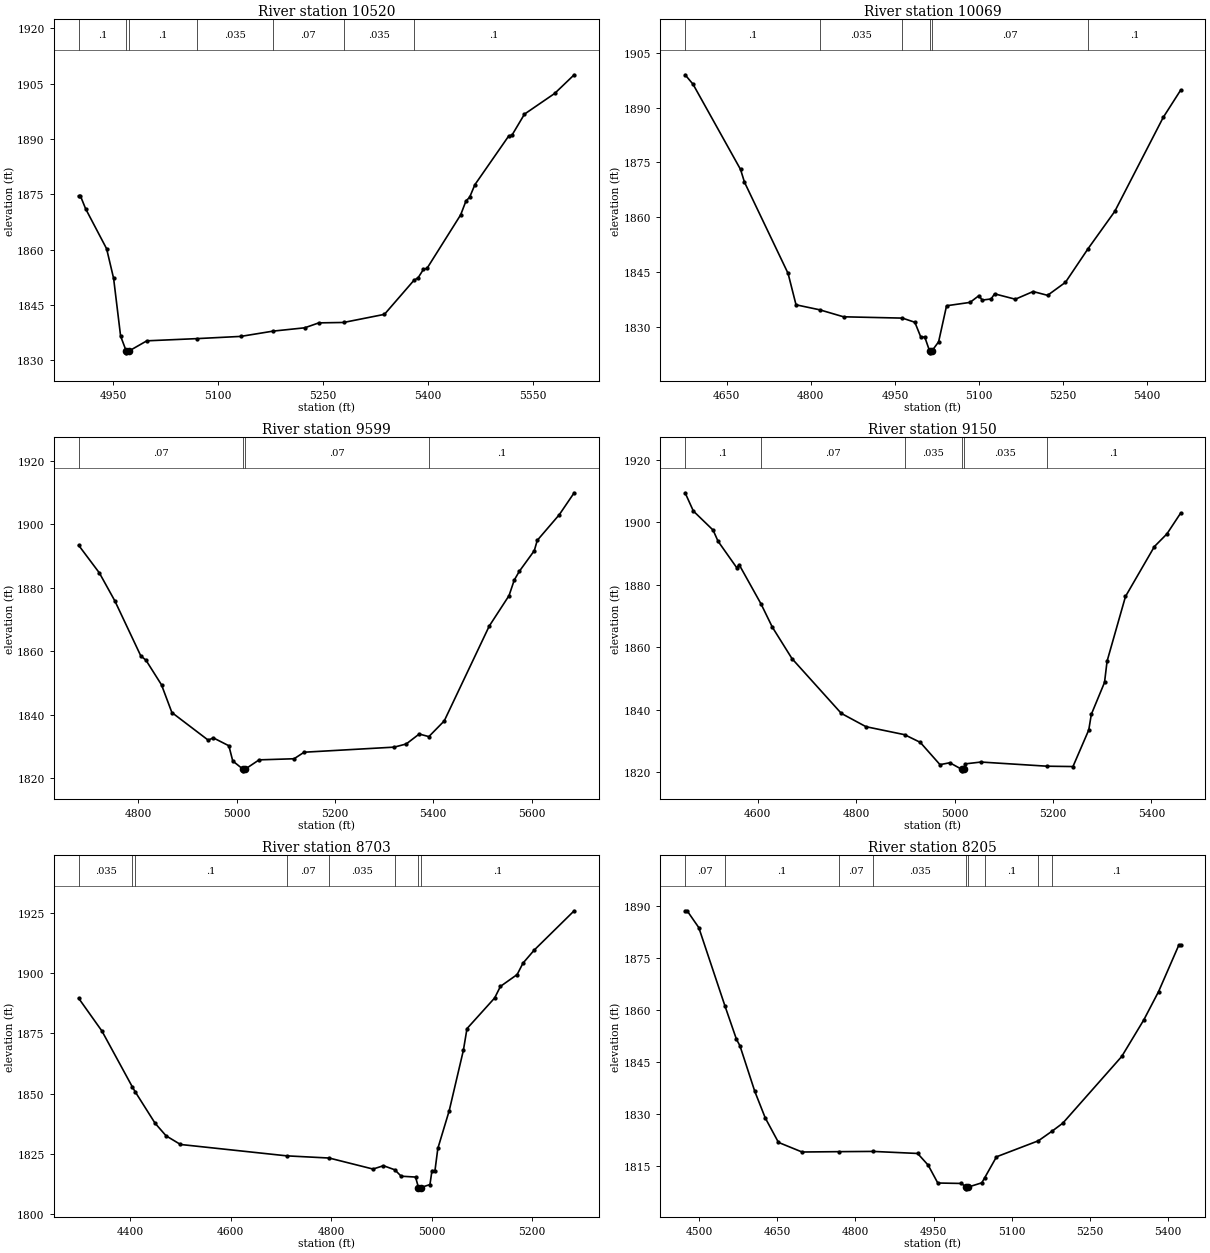
Type RM Length L Ch R = 1,10520,451,451,451
BEGIN DESCRIPTION:
Stream0323 21.0
END DESCRIPTION:
XS GIS Cut Line= 3
      1869324.98     13927925.00      1869425.00     13927925.00
      1870025.00     13927825.00
#Sta/Elev= 30
  4900.5 1874.58  4903.0 1874.58  4910.5 1871.06  4940.5 1860.22  4950.5 1852.18
  4960.5 1836.52  4968.5 1832.48  4968.8 1831.98  4972.5 1832.48  4998.0 1835.24
  5069.8 1835.84  5132.3 1836.44  5178.7 1837.88  5223.6 1838.77  5243.8 1840.11
  5279.2 1840.22  5337.6 1842.42  5379.7 1851.64  5385.8 1852.36  5393.4 1854.64
  5398.4 1854.88  5446.6 1869.43  5454.2 1873.22  5459.3 1874.16  5466.9 1877.60
  5515.0 1890.75  5520.1 1891.10  5537.8 1896.75  5580.9 1902.35  5608.8 1907.42
#Mann=7,-1,0
  4900.5     0.1       0  4968.5    0.05       0  4972.5     0.1       0
  5069.8   0.035       0  5178.7    0.07       0  5279.2   0.035       0
  5379.7     0.1       0
Bank Sta=4968.5,4972.5
Exp/Cntr=0.3,0.1

Type RM Length L Ch R = 1,10069,470,470,470
BEGIN DESCRIPTION:
Stream0323 20.0
END DESCRIPTION:
XS GIS Cut Line= 4
      1869225.02     13927975.02      1869525.00     13928275.00
      1869575.00     13928325.00      1869913.86     13928517.15
#Sta/Elev= 30
  4575.5 1898.96  4589.6 1896.39  4674.5 1873.05  4681.5 1869.57  4759.3 1844.62
  4773.5 1836.03  4815.8 1834.66  4858.3 1832.75  4963.5 1832.39  4985.6 1831.25
  4996.2 1827.21  5003.3 1827.21  5011.9 1823.39  5012.1 1822.89  5015.9 1823.39
  5028.0 1825.90  5042.2 1835.77  5084.1 1836.69  5100.0 1838.54  5105.8 1837.32
  5121.7 1837.63  5127.9 1839.03  5164.9 1837.56  5196.7 1839.66  5222.5 1838.62
  5254.4 1842.18  5294.8 1851.39  5342.4 1861.58  5428.9 1887.30  5460.0 1894.75
#Mann=6,-1,0
  4575.5     0.1       0  4815.8   0.035       0  4963.5    0.07       0
  5011.9    0.05       0  5015.9    0.07       0  5294.8     0.1       0
Bank Sta=5011.9,5015.9
Exp/Cntr=0.3,0.1

Type RM Length L Ch R = 1,9599,449,449,449
BEGIN DESCRIPTION:
Stream0323 19.0
END DESCRIPTION:
XS GIS Cut Line= 3
      1868925.05     13928574.98      1869225.00     13928475.00
      1869904.73     13928603.79
#Sta/Elev= 30
  4678.8 1893.40  4720.9 1884.70  4752.5 1875.86  4805.2 1858.55  4815.8 1857.17
  4847.4 1849.41  4868.5 1840.68  4942.3 1831.99  4952.8 1832.70  4984.4 1830.21
  4992.3 1825.42  5013.3 1822.81  5013.6 1822.31  5017.3 1822.81  5045.9 1825.77
  5117.1 1826.12  5137.5 1828.18  5320.7 1829.78  5345.1 1830.77  5371.6 1833.91
  5391.2 1833.10  5422.5 1838.04  5514.1 1867.95  5554.3 1877.53  5564.9 1882.43
  5575.1 1885.16  5605.7 1891.70  5611.7 1894.94  5656.5 1903.03  5686.8 1909.94
#Mann=4,-1,0
  4678.8    0.07       0  5013.3    0.05       0  5017.3    0.07       0
  5391.2     0.1       0
Bank Sta=5013.3,5017.3
Exp/Cntr=0.3,0.1

Type RM Length L Ch R = 1,9150,447,447,447
BEGIN DESCRIPTION:
Stream0323 18.0
END DESCRIPTION:
XS GIS Cut Line= 3
      1868828.18     13928906.12      1869375.00     13928875.00
      1869811.55     13928733.87
#Sta/Elev= 30
  4452.7 1909.40  4469.5 1903.56  4509.6 1897.46  4519.6 1893.92  4557.5 1885.47
  4562.5 1886.42  4607.0 1873.85  4629.8 1866.48  4669.9 1856.38  4770.0 1838.89
  4820.1 1834.64  4898.4 1832.09  4930.3 1829.64  4970.4 1822.51  4990.4 1823.11
  5014.4 1821.03  5014.7 1820.53  5018.4 1821.03  5021.7 1822.76  5053.7 1823.34
  5188.1 1822.01  5240.5 1821.90  5272.6 1833.60  5277.8 1838.59  5304.6 1848.78
  5309.8 1855.58  5347.2 1876.26  5405.9 1892.21  5431.3 1896.25  5459.2 1902.90
#Mann=6,-1,0
  4452.7     0.1       0  4607.0    0.07       0  4898.4   0.035       0
  5014.4   0.035       0  5018.4   0.035       0  5188.1     0.1       0
Bank Sta=5014.4,5018.4
Exp/Cntr=0.3,0.1

Type RM Length L Ch R = 1,8703,498,498,498
BEGIN DESCRIPTION:
Stream0323 17.0
END DESCRIPTION:
XS GIS Cut Line= 3
      1869176.98     13929371.69      1869725.00     13928925.00
      1869977.41     13928803.58
#Sta/Elev= 30
  4296.9 1889.62  4343.3 1876.01  4404.2 1852.71  4409.5 1850.83  4449.2 1837.74
  4471.1 1832.52  4499.8 1828.93  4711.5 1824.21  4796.1 1823.30  4883.3 1818.73
  4904.1 1820.12  4926.7 1818.42  4939.4 1815.76  4968.0 1815.41  4973.9 1811.02
  4974.2 1810.52  4977.9 1811.02  4996.7 1812.29  5000.7 1818.05  5006.7 1818.05
  5012.4 1827.27  5035.1 1842.96  5063.3 1868.00  5070.5 1877.01  5125.6 1889.73
  5137.1 1894.53  5170.4 1899.44  5182.0 1904.17  5204.6 1909.64  5284.0 1925.91
#Mann=8,-1,0
  4296.9   0.035       0  4404.2    0.07       0  4409.5     0.1       0
  4711.5    0.07       0  4796.1   0.035       0  4926.7     0.1       0
  4973.9    0.05       0  4977.9     0.1       0
Bank Sta=4973.9,4977.9
Exp/Cntr=0.3,0.1

Type RM Length L Ch R = 1,8205,484,484,484
BEGIN DESCRIPTION:
Stream0323 16.0
END DESCRIPTION:
XS GIS Cut Line= 3
      1869202.35     13929493.20      1869725.00     13929425.00
      1870024.97     13929125.03
#Sta/Elev= 30
  4472.9 1888.60  4476.8 1888.60  4499.2 1883.75  4549.4 1861.19  4571.4 1851.62
  4578.2 1849.70  4606.7 1836.57  4626.8 1828.92  4652.1 1821.88  4697.4 1819.11
  4767.8 1819.21  4833.8 1819.28  4919.3 1818.69  4939.5 1815.33  4958.0 1810.18
  5003.5 1810.05  5012.1 1809.00  5012.4 1808.50  5016.1 1809.00  5042.4 1810.23
  5047.8 1811.62  5070.7 1817.73  5151.2 1822.35  5177.9 1825.17  5198.0 1827.42
  5311.1 1846.63  5353.5 1857.17  5381.8 1865.31  5420.7 1878.71  5424.2 1878.71
#Mann=9,-1,0
  4472.9    0.07       0  4549.4     0.1       0  4767.8    0.07       0
  4833.8   0.035       0  5012.1   0.035       0  5016.1   0.035       0
  5047.8     0.1       0  5151.2    0.07       0  5177.9     0.1       0
Bank Sta=5012.1,5016.1
Exp/Cntr=0.3,0.1

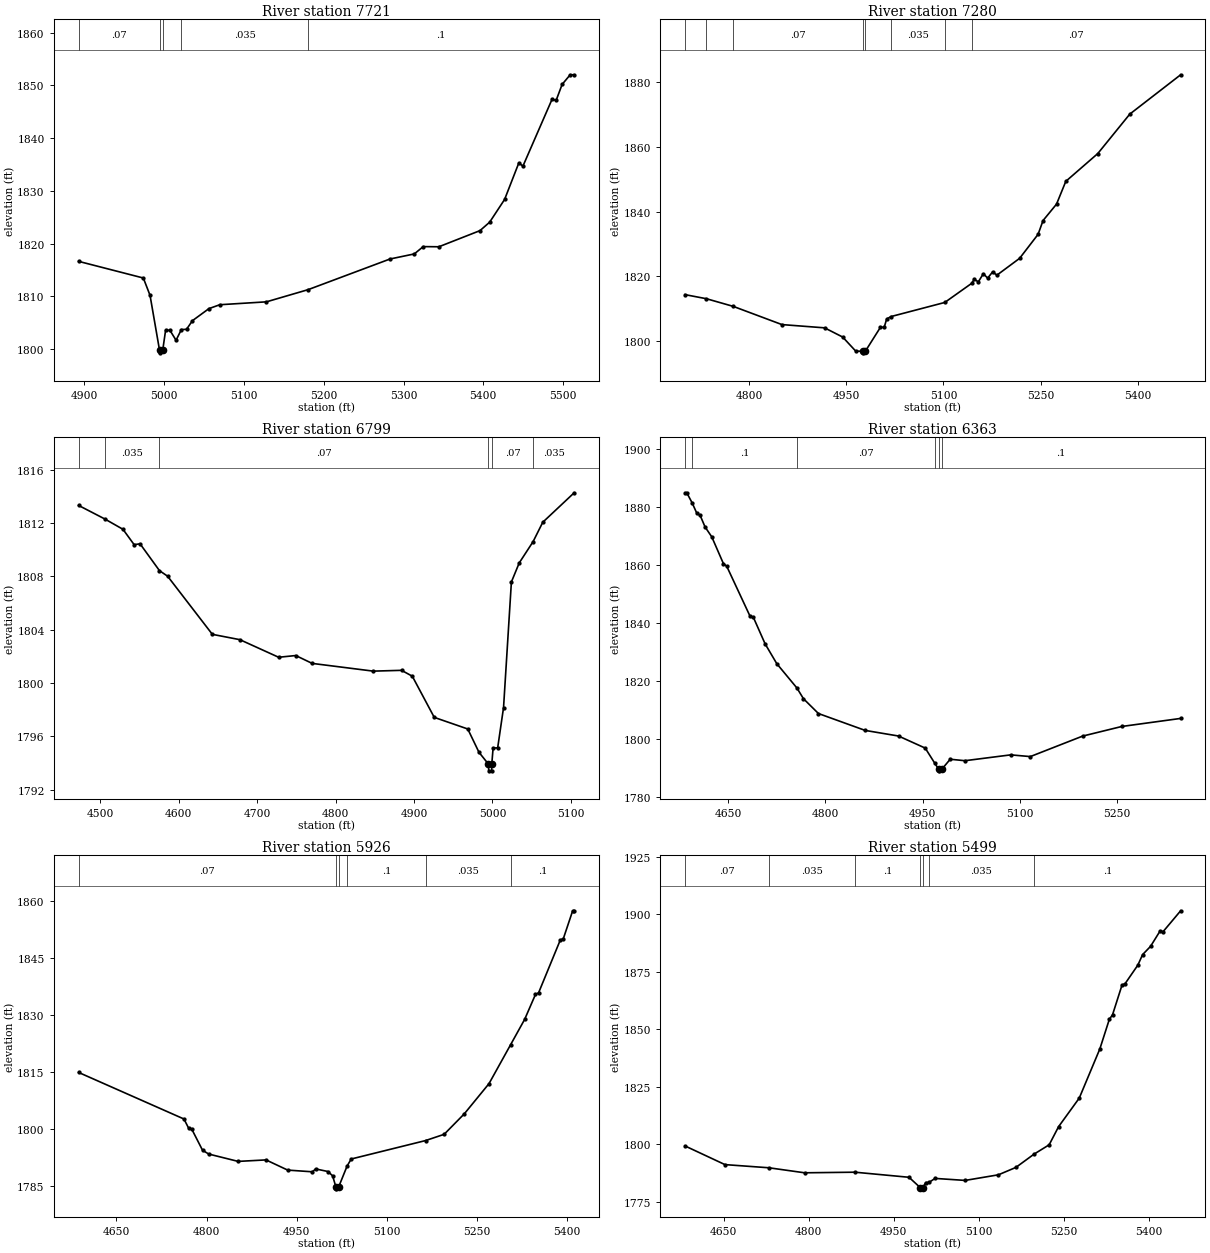
Type RM Length L Ch R = 1,7721,441,441,441
BEGIN DESCRIPTION:
Stream0323 15.0
END DESCRIPTION:
XS GIS Cut Line= 3
      1869624.98     13929925.01      1869725.00     13929875.00
      1870219.71     13929754.10
#Sta/Elev= 30
  4892.8 1816.61  4973.9 1813.45  4982.3 1810.16  4994.2 1799.75  4994.5 1799.25
  4998.2 1799.75  5001.8 1803.53  5007.2 1803.53  5014.9 1801.64  5021.6 1803.67
  5028.0 1803.71  5035.5 1805.36  5056.1 1807.64  5069.7 1808.38  5128.2 1808.93
  5180.4 1811.24  5283.1 1817.06  5313.5 1818.02  5324.7 1819.41  5344.3 1819.38
  5395.8 1822.44  5408.0 1824.05  5426.7 1828.36  5444.5 1835.28  5449.7 1834.69
  5486.2 1847.38  5491.3 1847.16  5498.8 1850.19  5508.9 1852.02  5513.9 1852.02
#Mann=5,-1,0
  4892.8    0.07       0  4994.2    0.05       0  4998.2    0.07       0
  5021.6   0.035       0  5180.4     0.1       0
Bank Sta=4994.2,4998.2
Exp/Cntr=0.3,0.1

Type RM Length L Ch R = 1,7280,481,481,481
BEGIN DESCRIPTION:
Stream0323 14.0
END DESCRIPTION:
XS GIS Cut Line= 3
      1869725.04     13930125.01      1870025.00     13930175.00
      1870375.02     13929874.98
#Sta/Elev= 30
  4701.1 1814.30  4734.0 1813.04  4775.4 1810.67  4850.6 1805.03  4916.5 1804.02
  4944.4 1801.17  4964.6 1796.80  4975.3 1796.78  4975.5 1796.28  4979.4 1796.78
  5002.7 1804.19  5008.5 1804.19  5012.3 1806.74  5018.9 1807.51  5102.0 1811.88
  5143.9 1817.85  5147.3 1819.04  5153.9 1818.28  5161.6 1820.79  5168.2 1819.41
  5175.9 1821.34  5182.5 1820.33  5217.6 1825.55  5246.1 1832.98  5253.8 1837.26
  5274.6 1842.34  5288.9 1849.39  5338.3 1858.00  5387.7 1870.21  5466.2 1882.39
#Mann=8,-1,0
  4701.1    0.07       0  4734.0   0.035       0  4775.4    0.07       0
  4975.3    0.05       0  4979.4    0.07       0  5018.9   0.035       0
  5102.0     0.1       0  5143.9    0.07       0
Bank Sta=4975.3,4979.4
Exp/Cntr=0.3,0.1

Type RM Length L Ch R = 1,6799,436,436,436
BEGIN DESCRIPTION:
Stream0323 13.0
END DESCRIPTION:
XS GIS Cut Line= 3
      1869624.98     13930274.98      1870025.00     13930625.00
      1870124.96     13930625.00
#Sta/Elev= 30
  4472.6 1813.31  4505.8 1812.30  4529.1 1811.52  4543.3 1810.37  4550.9 1810.43
  4575.6 1808.42  4586.0 1808.00  4643.0 1803.64  4678.1 1803.24  4727.5 1801.92
  4749.3 1802.05  4770.2 1801.46  4848.0 1800.88  4884.1 1800.94  4897.8 1800.50
  4925.8 1797.41  4968.5 1796.54  4982.8 1794.79  4994.9 1793.90  4995.2 1793.40
  4998.9 1793.40  4999.1 1793.90  5000.8 1795.12  5006.6 1795.12  5014.1 1798.15
  5024.1 1807.57  5034.1 1809.00  5051.8 1810.60  5064.1 1812.05  5104.1 1814.26
#Mann=6,-1,0
  4472.6    0.07       0  4505.8   0.035       0  4575.6    0.07       0
  4994.9    0.05       0  4999.1    0.07       0  5051.8   0.035       0
Bank Sta=4994.9,4999.1
Exp/Cntr=0.3,0.1

Type RM Length L Ch R = 1,6363,437,437,437
BEGIN DESCRIPTION:
Stream0323 12.0
END DESCRIPTION:
XS GIS Cut Line= 3
      1869325.02     13930825.01      1869725.00     13930925.00
      1870074.96     13930875.01
#Sta/Elev= 30
  4583.1 1884.76  4585.7 1884.76  4594.1 1881.23  4601.1 1877.76  4606.3 1876.99
  4614.0 1872.97  4624.3 1869.59  4642.3 1860.37  4647.5 1859.43  4683.6 1842.19
  4688.7 1841.82  4706.8 1832.72  4724.8 1825.91  4755.9 1817.54  4766.0 1813.85
  4789.2 1808.74  4861.4 1802.93  4912.9 1801.00  4954.2 1796.84  4969.0 1791.61
  4975.1 1789.51  4975.4 1789.01  4979.6 1789.51  4992.8 1793.00  5015.6 1792.50
  5086.3 1794.51  5116.6 1793.92  5197.4 1800.97  5258.0 1804.29  5348.9 1807.06
#Mann=6,-1,0
  4583.1    0.07       0  4594.1     0.1       0  4755.9    0.07       0
  4969.0     0.1       0  4975.1    0.05       0  4979.6     0.1       0
Bank Sta=4975.1,4979.6
Exp/Cntr=0.3,0.1

Type RM Length L Ch R = 1,5926,427,427,427
BEGIN DESCRIPTION:
Stream0323 11.0
END DESCRIPTION:
XS GIS Cut Line= 3
      1869524.98     13931325.00      1869925.00     13931225.00
      1870324.96     13931125.01
#Sta/Elev= 30
  4587.1 1814.79  4762.4 1802.54  4770.1 1800.14  4775.2 1799.92  4793.3 1794.32
  4803.6 1793.32  4852.5 1791.39  4898.9 1791.78  4935.0 1789.10  4976.2 1788.65
  4981.4 1789.41  5002.0 1788.73  5009.7 1787.60  5015.2 1784.67  5015.5 1784.17
  5019.8 1784.67  5033.9 1790.19  5040.7 1792.02  5164.4 1796.87  5195.3 1798.51
  5228.8 1803.89  5270.0 1811.85  5305.8 1822.05  5329.3 1828.75  5347.3 1835.31
  5352.5 1835.75  5388.5 1849.59  5393.7 1850.00  5409.2 1857.32  5411.7 1857.32
#Mann=6,-1,0
  4587.1    0.07       0  5015.2    0.05       0  5019.8    0.07       0
  5033.9     0.1       0  5164.4   0.035       0  5305.8     0.1       0
Bank Sta=5015.2,5019.8
Exp/Cntr=0.3,0.1

Type RM Length L Ch R = 1,5499,437,437,437
BEGIN DESCRIPTION:
Stream0323 10.0
END DESCRIPTION:
XS GIS Cut Line= 3
      1869675.04     13931724.98      1870075.00     13931575.00
      1870475.03     13931374.99
#Sta/Elev= 30
  4582.1 1799.23  4652.4 1791.14  4730.0 1789.76  4793.0 1787.58  4881.8 1787.84
  4977.2 1785.63  4997.2 1781.11  4997.5 1780.61  5001.8 1781.11  5006.6 1783.33
  5012.2 1783.38  5023.2 1785.14  5076.3 1784.27  5135.0 1786.71  5165.8 1789.92
  5197.9 1795.70  5224.5 1799.74  5241.2 1807.65  5277.6 1820.03  5313.9 1841.38
  5330.7 1854.28  5336.3 1856.22  5353.0 1869.09  5358.6 1869.80  5381.0 1877.81
  5389.4 1882.38  5403.4 1885.96  5420.1 1892.59  5425.7 1892.39  5456.5 1901.42
#Mann=7,-1,0
  4582.1    0.07       0  4730.0   0.035       0  4881.8     0.1       0
  4997.2    0.05       0  5001.8     0.1       0  5012.2   0.035       0
  5197.9     0.1       0
Bank Sta=4997.2,5001.8
Exp/Cntr=0.3,0.1

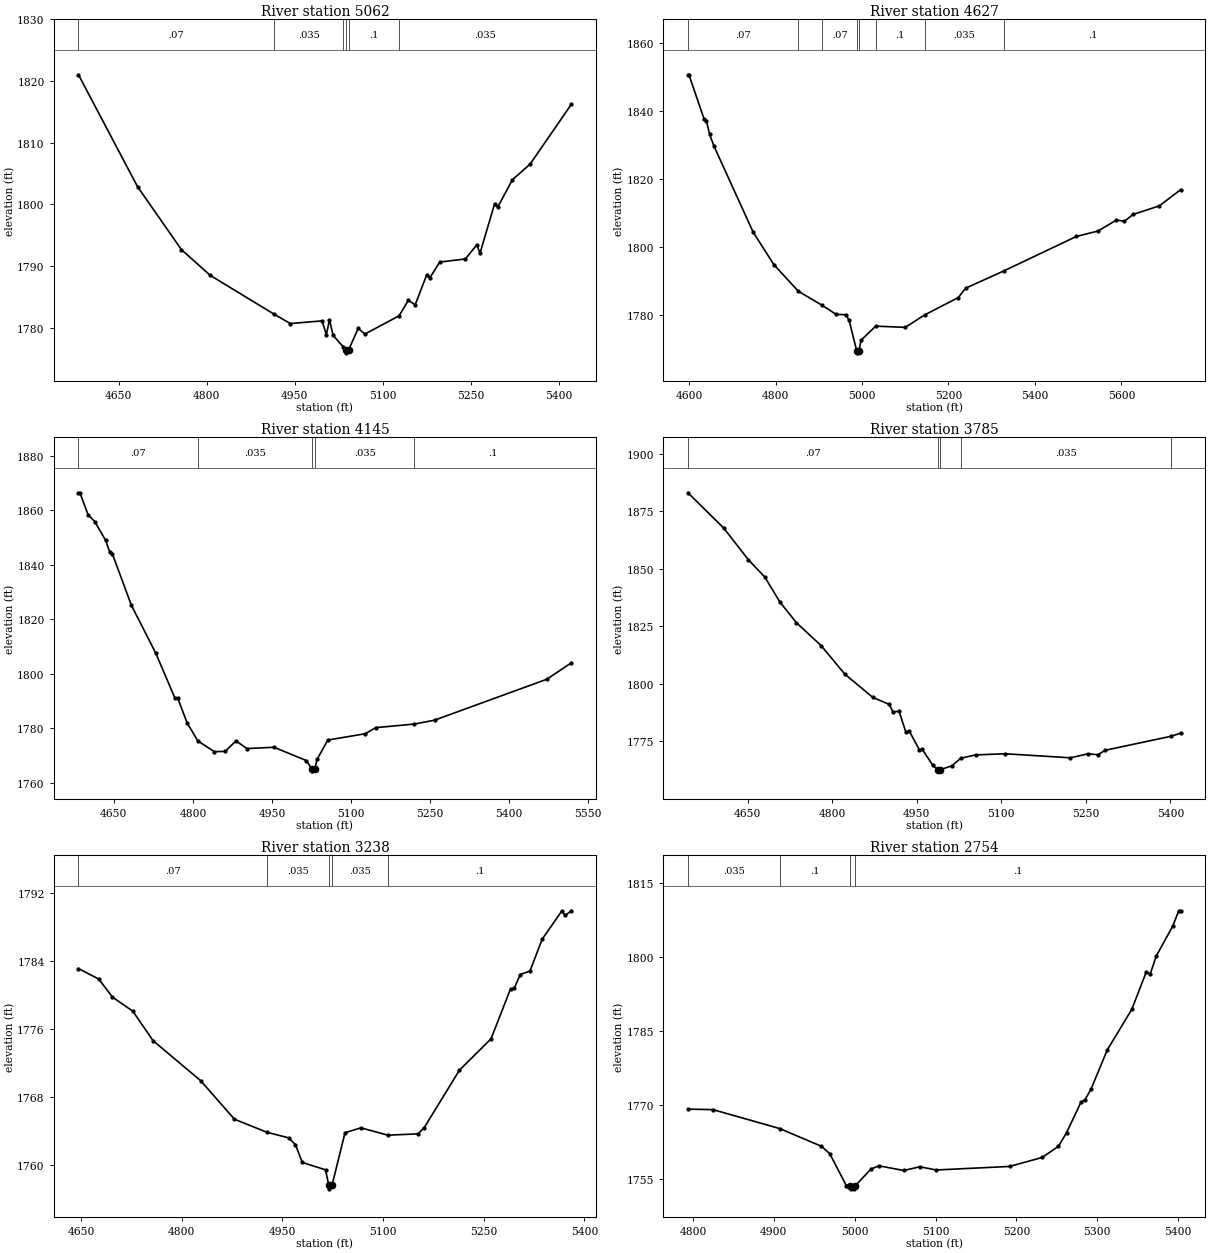
Type RM Length L Ch R = 1,5062,435,435,435
BEGIN DESCRIPTION:
Stream0323 9.0
END DESCRIPTION:
XS GIS Cut Line= 3
      1869524.97     13931824.99      1869925.00     13931925.00
      1870324.96     13931775.02
#Sta/Elev= 30
  4581.5 1820.99  4682.0 1802.86  4756.8 1792.65  4805.7 1788.49  4914.5 1782.19
  4942.3 1780.67  4996.5 1781.10  5003.6 1778.85  5009.0 1781.25  5015.2 1778.75
  5032.4 1776.89  5036.9 1776.42  5037.2 1775.92  5041.6 1776.42  5057.9 1779.87
  5069.5 1778.98  5127.5 1781.92  5143.4 1784.44  5154.9 1783.69  5174.5 1788.55
  5179.9 1788.07  5196.8 1790.64  5240.4 1791.13  5260.0 1793.45  5265.3 1792.06
  5290.2 1800.05  5295.6 1799.55  5320.5 1803.97  5350.7 1806.51  5421.0 1816.22
#Mann=6,-1,0
  4581.5    0.07       0  4914.5   0.035       0  5032.4     0.1       0
  5036.9   0.035       0  5041.6     0.1       0  5127.5   0.035       0
Bank Sta=5036.9,5041.6
Exp/Cntr=0.3,0.1

Type RM Length L Ch R = 1,4627,482,482,482
BEGIN DESCRIPTION:
Stream0323 8.0
END DESCRIPTION:
XS GIS Cut Line= 3
      1869425.00     13932375.00      1869825.00     13932325.00
      1870554.07     13932217.95
#Sta/Elev= 30
  4597.3 1850.64  4599.8 1850.64  4635.1 1837.48  4640.1 1837.06  4647.7 1833.05
  4657.8 1829.58  4748.5 1804.23  4796.3 1794.70  4852.9 1786.87  4907.8 1782.75
  4939.9 1780.09  4962.6 1779.96  4970.2 1778.32  4988.0 1769.24  4988.3 1768.74
  4992.7 1769.24  4997.9 1772.44  5031.7 1776.61  5100.0 1776.24  5144.8 1779.90
  5222.8 1785.03  5239.6 1787.77  5328.2 1792.88  5495.7 1803.01  5546.2 1804.64
  5588.6 1807.86  5606.8 1807.49  5627.1 1809.50  5687.7 1812.03  5737.3 1816.83
#Mann=8,-1,0
  4597.3    0.07       0  4852.9     0.1       0  4907.8    0.07       0
  4988.0    0.05       0  4992.7    0.07       0  5031.7     0.1       0
  5144.8   0.035       0  5328.2     0.1       0
Bank Sta=4988,4992.7
Exp/Cntr=0.3,0.1

Type RM Length L Ch R = 1,4145,360,360,360
BEGIN DESCRIPTION:
Stream0323 7.0
END DESCRIPTION:
XS GIS Cut Line= 3
      1869424.98     13932674.99      1869825.00     13932775.00
      1870341.40     13932858.23
#Sta/Elev= 30
  4582.9 1866.40  4585.5 1866.40  4601.0 1858.38  4613.8 1855.84  4634.5 1848.90
  4642.2 1844.58  4647.3 1843.94  4683.4 1825.04  4729.8 1807.44  4765.9 1791.02
  4771.0 1791.15  4789.1 1781.92  4809.3 1775.35  4840.6 1771.40  4861.2 1771.47
  4881.8 1775.35  4902.5 1772.52  4954.0 1773.00  5015.5 1768.11  5026.2 1764.85
  5026.6 1764.35  5031.2 1764.85  5035.7 1768.58  5056.0 1775.65  5126.9 1777.96
  5147.2 1780.21  5220.2 1781.51  5258.6 1782.95  5471.5 1797.95  5518.3 1803.99
#Mann=5,-1,0
  4582.9    0.07       0  4809.3   0.035       0  5026.2   0.035       0
  5031.2   0.035       0  5220.2     0.1       0
Bank Sta=5026.2,5031.2
Exp/Cntr=0.3,0.1

Type RM Length L Ch R = 1,3785,547,547,547
BEGIN DESCRIPTION:
Stream0323 6.0
END DESCRIPTION:
XS GIS Cut Line= 4
      1869324.99     13932724.99      1869549.90     13933024.87
      1869725.69     13933099.83      1870025.03     13933024.99
#Sta/Elev= 30
  4544.0 1883.14  4607.6 1867.81  4651.3 1854.02  4680.5 1846.47  4707.6 1835.50
  4736.7 1826.59  4780.5 1816.64  4822.1 1804.33  4872.1 1794.13  4901.3 1791.09
  4907.6 1787.92  4918.8 1788.01  4930.9 1778.94  4936.3 1779.70  4954.5 1771.43
  4959.9 1771.53  4978.1 1764.76  4987.1 1762.68  4987.5 1762.18  4992.1 1762.68
  5012.6 1764.41  5028.1 1767.65  5054.4 1769.11  5106.9 1769.61  5222.6 1767.85
  5253.5 1769.56  5271.6 1769.21  5284.5 1771.13  5401.7 1777.24  5418.5 1778.60
#Mann=5,-1,0
  4544.0    0.07       0  4987.1    0.05       0  4992.1    0.07       0
  5028.1   0.035       0  5401.7     0.1       0
Bank Sta=4987.1,4992.1
Exp/Cntr=0.3,0.1

Type RM Length L Ch R = 1,3238,484,484,484
BEGIN DESCRIPTION:
Stream0323 5.0
END DESCRIPTION:
XS GIS Cut Line= 3
      1869474.96     13933575.01      1869825.00     13933525.00
      1870175.01     13933374.99
#Sta/Elev= 30
  4646.3 1783.13  4676.6 1781.89  4696.9 1779.77  4727.2 1778.11  4757.5 1774.63
  4828.2 1769.93  4878.7 1765.38  4927.2 1763.84  4959.5 1763.19  4969.6 1762.38
  4979.7 1760.29  5014.4 1759.42  5019.0 1757.68  5019.4 1757.18  5024.3 1757.68
  5043.4 1763.79  5067.0 1764.37  5107.3 1763.50  5152.2 1763.66  5161.3 1764.38
  5213.9 1771.16  5261.0 1774.86  5290.0 1780.73  5295.5 1780.81  5304.5 1782.43
  5319.0 1782.84  5337.2 1786.60  5366.2 1789.89  5371.6 1789.40  5380.7 1789.94
#Mann=5,-1,0
  4646.3    0.07       0  4927.2   0.035       0  5019.0   0.035       0
  5024.3   0.035       0  5107.3     0.1       0
Bank Sta=5019,5024.3
Exp/Cntr=0.3,0.1

Type RM Length L Ch R = 1,2754,423,423,423
BEGIN DESCRIPTION:
Stream0323 4.0
END DESCRIPTION:
XS GIS Cut Line= 3
      1869724.97     13934025.01      1869925.00     13933975.00
      1870325.00     13933925.00
#Sta/Elev= 30
  4793.8 1769.13  4824.8 1769.03  4907.2 1765.20  4958.8 1761.61  4969.1 1760.13
  4989.7 1753.62  4994.7 1753.48  4995.2 1752.98  4999.7 1752.98  5000.1 1753.48
  5020.1 1757.00  5030.2 1757.64  5060.5 1756.70  5080.6 1757.45  5100.8 1756.80
  5191.5 1757.52  5231.8 1759.34  5251.9 1761.60  5262.0 1764.39  5279.6 1770.49
  5284.7 1771.05  5292.2 1773.20  5312.4 1781.18  5342.6 1789.36  5360.3 1796.87
  5365.3 1796.50  5372.9 1800.18  5393.0 1806.15  5400.6 1809.32  5403.1 1809.32
#Mann=4,-1,0
  4793.8   0.035       0  4907.2     0.1       0  4994.7    0.05       0
  5000.1     0.1       0
Bank Sta=4994.7,5000.1
Exp/Cntr=0.3,0.1