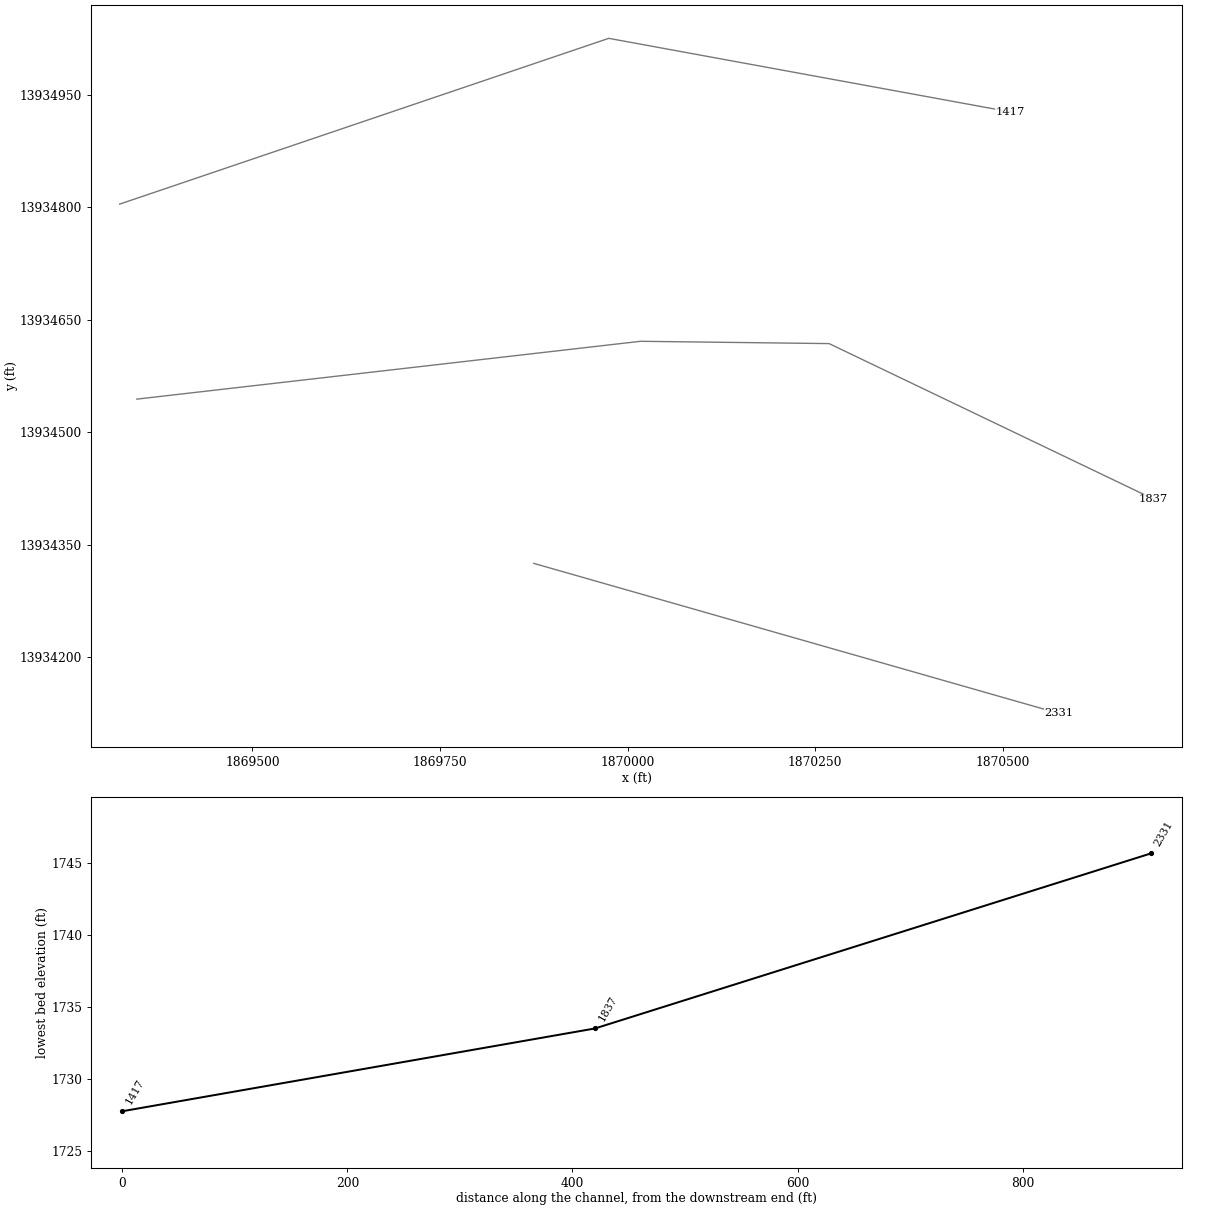
HEC-RAS study Stream0323.prj: Stream0323 Base Level Engineering

--- Stream0323.g01 (geometry) --- (continued)

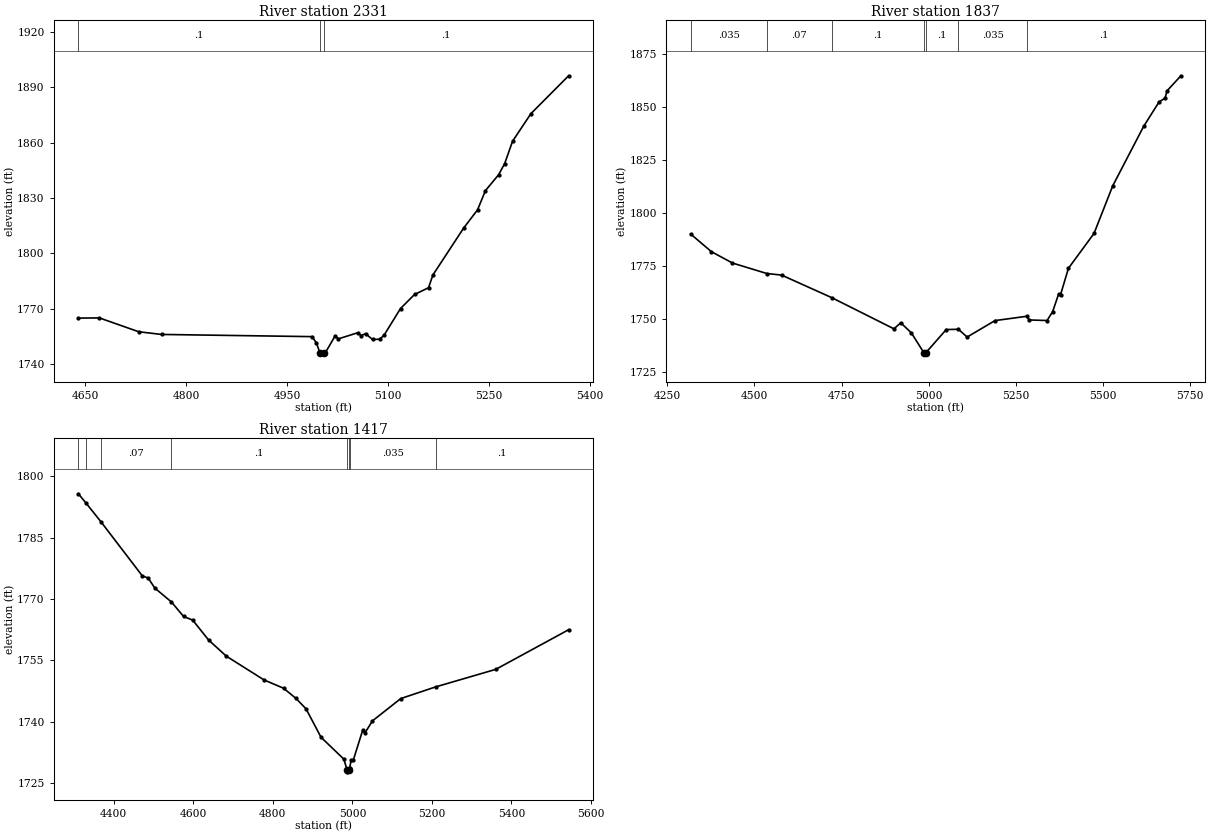
Type RM Length L Ch R = 1,2331,494,494,494
BEGIN DESCRIPTION:
Stream0323 3.0
END DESCRIPTION:
XS GIS Cut Line= 3
      1869875.03     13934324.99      1870225.00     13934225.00
      1870575.02     13934124.99
#Sta/Elev= 30
  4639.9 1765.01  4671.1 1765.12  4729.6 1757.62  4763.4 1756.17  4987.0 1754.98
  4993.5 1751.50  4998.6 1746.17  4999.0 1745.67  5004.0 1746.17  5006.5 1746.17
  5020.8 1755.14  5026.0 1753.78  5054.6 1757.06  5059.8 1755.58  5066.3 1756.60
  5076.7 1753.45  5087.1 1753.58  5093.6 1755.61  5118.3 1770.21  5139.1 1777.79
  5159.9 1781.46  5166.4 1788.37  5211.9 1813.68  5232.7 1823.63  5244.4 1834.02
  5263.9 1842.58  5273.0 1848.68  5284.7 1860.78  5312.0 1875.71  5367.9 1896.18
#Mann=3,-1,0
  4639.9     0.1       0  4998.6    0.05       0  5004.0     0.1       0
Bank Sta=4998.6,5004
Exp/Cntr=0.3,0.1

Type RM Length L Ch R = 1,1837,420,420,420
BEGIN DESCRIPTION:
Stream0323 2.0
END DESCRIPTION:
XS GIS Cut Line= 4
      1869345.79     13934543.97      1870017.35     13934621.07
      1870268.79     13934618.00      1870701.45     13934410.66
#Sta/Elev= 30
  4317.0 1790.00  4376.6 1781.68  4437.0 1776.33  4535.6 1771.39  4577.9 1770.65
  4721.8 1760.02  4900.5 1745.31  4920.1 1748.15  4950.3 1743.42  4986.5 1734.01
  4987.0 1733.51  4992.0 1734.01  5050.6 1744.97  5085.5 1745.09  5110.6 1741.43
  5190.6 1749.19  5282.2 1751.23  5288.1 1749.49  5340.0 1749.22  5356.1 1753.44
  5373.2 1761.70  5378.7 1761.40  5401.4 1773.86  5474.9 1790.32  5528.5 1812.73
  5617.3 1840.80  5661.7 1852.34  5678.8 1854.11  5684.4 1857.54  5724.2 1864.64
#Mann=7,-1,0
  4317.0   0.035       0  4535.6    0.07       0  4721.8     0.1       0
  4986.5    0.05       0  4992.0     0.1       0  5085.5   0.035       0
  5282.2     0.1       0
Bank Sta=4986.5,4992
Exp/Cntr=0.3,0.1

Type RM Length L Ch R = 1,1417,0,0,0
BEGIN DESCRIPTION:
Stream0323 1.0
END DESCRIPTION:
XS GIS Cut Line= 3
      1869322.85     13934803.95      1869975.00     13935025.00
      1870510.00     13934926.99
#Sta/Elev= 30
  4311.1 1795.76  4330.1 1793.52  4367.9 1788.91  4471.8 1775.69  4486.7 1775.14
  4503.4 1772.69  4545.1 1769.30  4575.6 1765.76  4598.5 1764.87  4638.4 1760.01
  4682.9 1756.06  4778.0 1750.23  4826.9 1748.21  4858.3 1745.71  4883.6 1743.15
  4921.2 1736.21  4978.6 1730.86  4986.5 1728.26  4986.9 1727.76  4992.0 1728.26
  4992.8 1728.63  4997.1 1730.59  5002.2 1730.59  5026.3 1738.06  5031.4 1737.24
  5050.5 1740.23  5121.7 1745.68  5209.2 1748.53  5360.5 1752.82  5543.6 1762.51
#Mann=8,-1,0
  4311.1   0.035       0  4330.1     0.1       0  4367.9    0.07       0
  4545.1     0.1       0  4986.5   0.035       0  4992.0     0.1       0
  4992.8   0.035       0  5209.2     0.1       0
Bank Sta=4986.5,4992
Exp/Cntr=0.3,0.1

Chan Stop Cuts=-1