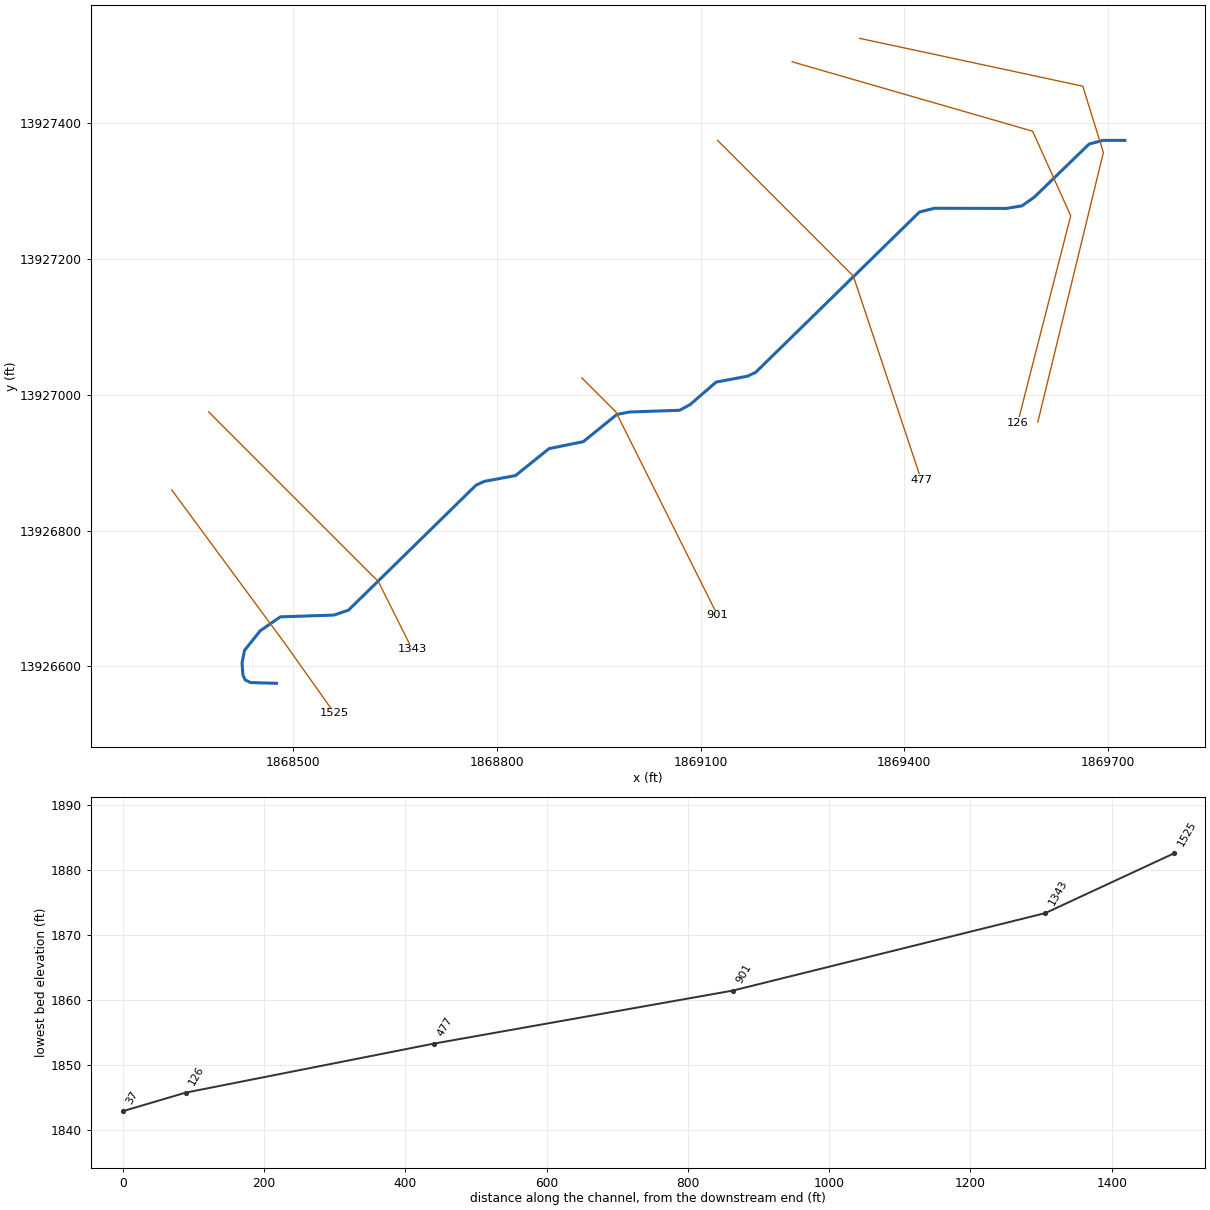
--- Stream0324.prj (project) ---

Proj Title=Stream0324 Base Level Engineering
Current Plan=p01
Default Exp/Contr=0.3,0.1
English Units
Geom File=g01
Flow File=f01
Plan File=p01
BEGIN DESCRIPTION:
Stream0324
END DESCRIPTION:

--- Stream0324.p01 (plan) ---

Plan Title=Multiple Run
Short Identifier=Multiple
Geom File=g01
Flow File=f01
Subcritical Flow
K Sum by GR= 0
Std Step Tol= 0.01
Critical Tol= 0.01
Num of Std Step Trials= 20
Max Error Tol= 0.3
Flow Tol Ratio= 0.001
Split Flow NTrial= 30
Split Flow Tol= 0.02
Split Flow Ratio= 0.02
Log Output Level= 0
Friction Slope Method= 1
Unsteady Friction Slope Method= 2
Unsteady Bridges Friction Slope Method= 1
Parabolic Critical Depth
Global Vel Dist=  1 , 1 , 1
Global Log Level= 0
CheckData=True
Encroach Param= -1, 0, 0, 0
BEGIN DESCRIPTION:
Multiple Run
END DESCRIPTION:

--- Stream0324.f01 (steady flow) ---

Flow Title=Multiple
Number of Profiles=7
Profile Names=10-year,25-year,50-year,1pct_min,100-year,1pct_plu,500-year
River Rch & RM= Stream0324,Reach-1,1525
     353     561     747     484     966    1927    1585
River Rch & RM= Stream0324,Reach-1,37
    1348    2353    3334    2285    4559    9097    8420
Boundary for River Rch & Prof#=Stream0324,Reach-1,1
Up Type=0
Dn Type=3
Dn Slope=0.005
Boundary for River Rch & Prof#=Stream0324,Reach-1,2
Up Type=0
Dn Type=3
Dn Slope=0.005
Boundary for River Rch & Prof#=Stream0324,Reach-1,3
Up Type=0
Dn Type=3
Dn Slope=0.005
Boundary for River Rch & Prof#=Stream0324,Reach-1,4
Up Type=0
Dn Type=3
Dn Slope=0.005
Boundary for River Rch & Prof#=Stream0324,Reach-1,5
Up Type=0
Dn Type=3
Dn Slope=0.005
Boundary for River Rch & Prof#=Stream0324,Reach-1,6
Up Type=0
Dn Type=3
Dn Slope=0.005
Boundary for River Rch & Prof#=Stream0324,Reach-1,7
Up Type=0
Dn Type=3
Dn Slope=0.005

--- Stream0324.g01 (geometry) ---

Geom Title=Existing Conditions

River Reach=Stream0324,Reach-1
Reach XY= 30
      1868475.00     13926575.00      1868436.90     13926576.08
      1868428.91     13926579.96      1868425.61     13926586.83
      1868424.25     13926604.92      1868427.86     13926623.48
      1868450.86     13926652.24      1868480.67     13926672.92
      1868559.78     13926675.53      1868581.17     13926682.86
      1868768.94     13926866.86      1868781.03     13926872.50
      1868827.19     13926881.10      1868876.72     13926920.84
      1868927.18     13926931.12      1868976.58     13926971.17
      1868995.10     13926974.77      1869069.03     13926977.33
      1869084.65     13926985.84      1869122.83     13927018.86
      1869168.97     13927027.50      1869181.06     13927033.14
      1869422.55     13927269.53      1869444.99     13927275.02
      1869550.11     13927274.73      1869573.53     13927278.54
      1869591.76     13927291.44      1869672.49     13927369.67
      1869693.12     13927375.07      1869725.00     13927375.00

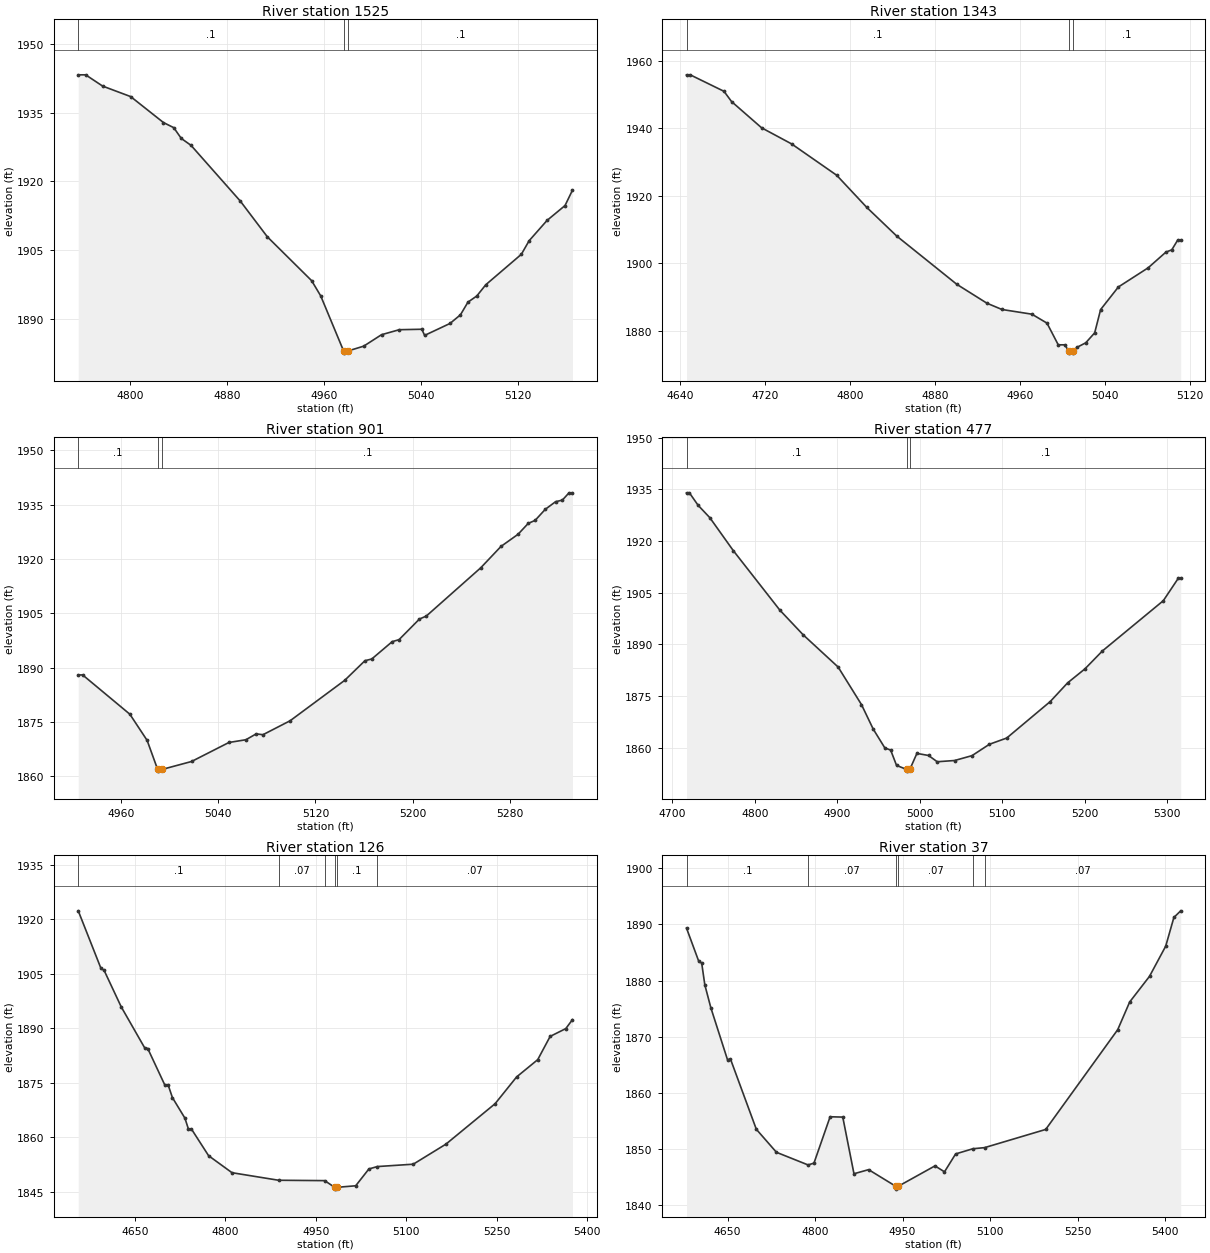
Type RM Length L Ch R = 1,1525,182,182,182
BEGIN DESCRIPTION:
Stream0324 4.0
END DESCRIPTION:
XS GIS Cut Line= 3
      1868320.74     13926859.81      1868488.71     13926631.94
      1868560.49     13926530.68
#Sta/Elev= 30
  4757.4 1943.27  4763.5 1943.27  4777.5 1940.81  4800.6 1938.52  4827.6 1932.86
  4836.1 1931.74  4842.3 1929.39  4850.3 1927.89  4891.0 1915.70  4913.2 1907.93
  4949.7 1898.36  4957.2 1895.03  4976.0 1883.05  4976.3 1882.55  4980.0 1883.05
  4992.6 1884.07  5007.3 1886.57  5021.9 1887.66  5040.5 1887.76  5042.8 1886.42
  5063.7 1889.02  5072.3 1890.90  5078.5 1893.67  5085.8 1895.02  5093.2 1897.47
  5122.5 1904.11  5128.9 1907.07  5143.7 1911.51  5158.5 1914.75  5164.6 1918.09
#Mann=3,-1,0
  4757.4     0.1       0  4976.0    0.05       0  4980.0     0.1       0
Bank Sta=4976,4980
Exp/Cntr=0.3,0.1

Type RM Length L Ch R = 1,1343,442,442,442
BEGIN DESCRIPTION:
Stream0324 3.0
END DESCRIPTION:
XS GIS Cut Line= 3
      1868375.02     13926974.98      1868625.00     13926725.00
      1868674.99     13926625.03
#Sta/Elev= 30
  4646.2 1955.83  4649.7 1955.83  4681.5 1950.94  4688.6 1947.91  4716.9 1940.13
  4745.2 1935.35  4787.6 1926.07  4815.9 1916.55  4844.2 1908.03  4900.7 1893.75
  4929.0 1888.16  4943.2 1886.29  4971.4 1884.90  4985.6 1882.25  4996.2 1875.82
  5002.5 1875.82  5006.1 1873.86  5006.4 1873.36  5009.9 1873.36  5010.1 1873.86
  5013.7 1875.05  5022.1 1876.42  5030.5 1879.37  5036.1 1886.27  5052.8 1892.96
  5080.8 1898.63  5097.6 1903.30  5103.1 1903.97  5108.7 1906.87  5111.5 1906.87
#Mann=3,-1,0
  4646.2     0.1       0  5006.1    0.05       0  5010.1     0.1       0
Bank Sta=5006.1,5010.1
Exp/Cntr=0.3,0.1

Type RM Length L Ch R = 1,901,424,424,424
BEGIN DESCRIPTION:
Stream0324 2.0
END DESCRIPTION:
XS GIS Cut Line= 3
      1868924.99     13927025.01      1868975.00     13926975.00
      1869124.98     13926675.04
#Sta/Elev= 30
  4925.1 1888.01  4928.7 1888.01  4967.5 1877.16  4981.7 1869.93  4990.3 1861.94
  4990.5 1861.44  4994.3 1861.94  5018.2 1864.10  5048.9 1869.35  5062.9 1870.11
  5071.3 1871.73  5076.9 1871.50  5099.2 1875.35  5144.0 1886.50  5160.7 1891.94
  5166.3 1892.41  5183.1 1897.20  5188.7 1897.75  5205.5 1903.45  5211.1 1904.26
  5255.8 1917.58  5272.5 1923.50  5286.5 1926.85  5294.9 1929.87  5300.5 1930.68
  5308.9 1933.75  5317.3 1935.84  5322.9 1936.29  5328.4 1938.30  5331.2 1938.30
#Mann=3,-1,0
  4925.1     0.1       0  4990.3    0.05       0  4994.3     0.1       0
Bank Sta=4990.3,4994.3
Exp/Cntr=0.3,0.1

Type RM Length L Ch R = 1,477,351,351,351
BEGIN DESCRIPTION:
Stream0324 1.0
END DESCRIPTION:
XS GIS Cut Line= 3
      1869125.00     13927375.00      1869325.00     13927175.00
      1869425.01     13926874.97
#Sta/Elev= 30
  4717.2 1933.98  4720.7 1933.98  4731.3 1930.35  4745.5 1926.76  4773.8 1917.25
  4830.3 1899.97  4858.6 1892.80  4901.0 1883.45  4929.3 1872.56  4943.5 1865.47
  4957.6 1860.00  4964.7 1859.35  4971.8 1854.93  4983.9 1853.76  4984.1 1853.26
  4987.9 1853.76  4996.5 1858.40  5010.6 1857.80  5021.1 1855.98  5042.2 1856.34
  5063.3 1857.75  5084.4 1861.05  5105.4 1862.86  5158.1 1873.43  5179.2 1878.86
  5200.3 1882.94  5221.4 1888.12  5295.2 1902.69  5313.6 1909.28  5316.3 1909.28
#Mann=3,-1,0
  4717.2     0.1       0  4983.9    0.05       0  4987.9     0.1       0
Bank Sta=4983.9,4987.9
Exp/Cntr=0.3,0.1

Type RM Length L Ch R = 1,126,89,89,89
BEGIN DESCRIPTION:
Stream0324 0.0
END DESCRIPTION:
XS GIS Cut Line= 4
      1869234.97     13927490.76      1869589.20     13927388.53
      1869645.31     13927263.97      1869567.30     13926959.19
#Sta/Elev= 30
  4556.0 1922.31  4593.6 1906.50  4598.8 1905.96  4627.3 1895.88  4666.1 1884.63
  4671.3 1884.42  4699.8 1874.31  4705.0 1874.45  4712.2 1870.92  4733.0 1865.24
  4738.6 1862.35  4743.8 1862.26  4772.3 1854.91  4811.1 1850.24  4888.4 1848.16
  4964.8 1848.06  4981.4 1846.22  4981.6 1845.72  4985.4 1846.22  5016.3 1846.64
  5038.2 1851.27  5052.2 1851.93  5111.8 1852.58  5166.0 1858.10  5247.6 1869.23
  5283.3 1876.60  5318.3 1881.35  5338.9 1887.75  5364.9 1889.90  5375.9 1892.36
#Mann=6,-1,0
  4556.0     0.1       0  4888.4    0.07       0  4964.8     0.1       0
  4981.4    0.05       0  4985.4     0.1       0  5052.2    0.07       0
Bank Sta=4981.4,4985.4
Exp/Cntr=0.3,0.1

Type RM Length L Ch R = 1,37,0,0,0
BEGIN DESCRIPTION:
Stream0324 0.1
END DESCRIPTION:
XS GIS Cut Line= 4
      1869334.27     13927525.38      1869663.09     13927454.84
      1869693.47     13927357.18      1869596.89     13926960.02
#Sta/Elev= 30
  4579.6 1889.35  4600.5 1883.46  4605.6 1883.14  4611.0 1879.24  4621.3 1875.17
  4649.9 1865.90  4655.0 1866.02  4699.3 1853.52  4733.8 1849.42  4788.0 1847.17
  4798.1 1847.49  4825.8 1855.75  4847.5 1855.69  4866.7 1845.60  4891.8 1846.33
  4938.5 1843.36  4938.8 1842.86  4942.5 1843.36  5005.6 1847.00  5021.9 1845.94
  5041.0 1849.13  5070.5 1850.05  5090.6 1850.25  5195.4 1853.49  5318.9 1871.26
  5339.4 1876.19  5373.4 1880.76  5401.2 1886.14  5415.2 1891.25  5426.9 1892.43
#Mann=6,-1,0
  4579.6     0.1       0  4788.0    0.07       0  4938.5    0.05       0
  4942.5    0.07       0  5070.5     0.1       0  5090.6    0.07       0
Bank Sta=4938.5,4942.5
Exp/Cntr=0.3,0.1

Chan Stop Cuts=-1