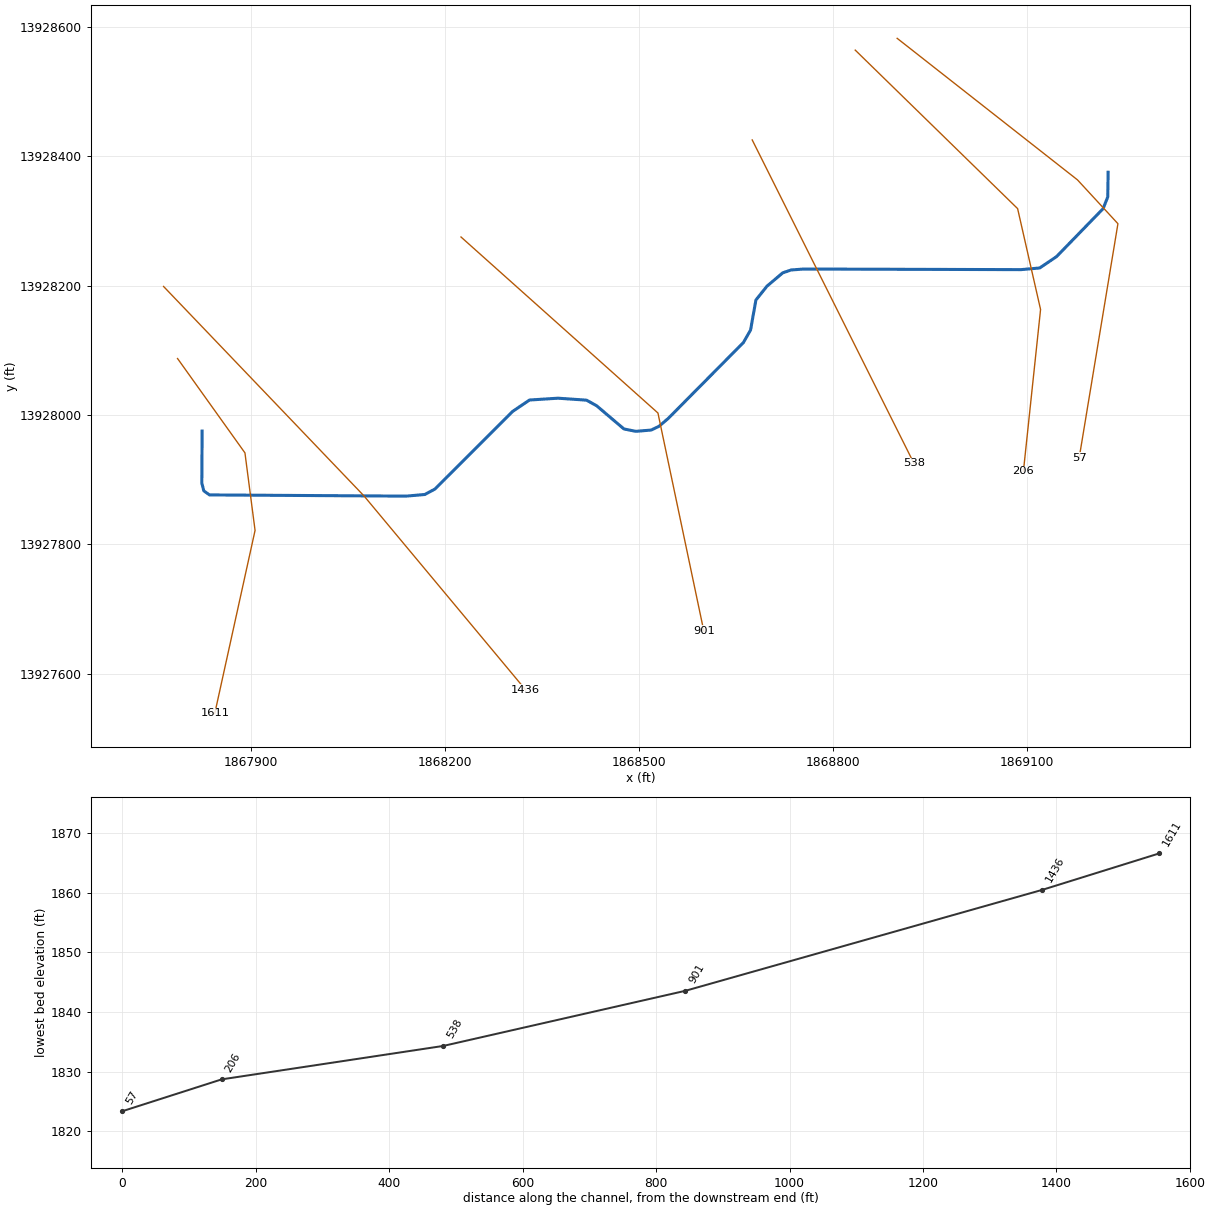
--- Stream0325.prj (project) ---

Proj Title=Stream0325 Base Level Engineering
Current Plan=p01
Default Exp/Contr=0.3,0.1
English Units
Geom File=g01
Flow File=f01
Plan File=p01
Y Axis Title=Elevation
X Axis Title(PF)=Main Channel Distance
X Axis Title(XS)=Station
BEGIN DESCRIPTION:
Stream0325
END DESCRIPTION:
DSS Export Rating Curves= 0
DSS Export Rating Curve Sorted= 0
DSS Export Volume Flow Curves= 0
DXF OffsetX= 0
DXF OffsetY= 0
DXF ScaleX= 1
DXF ScaleY= 10

--- Stream0325.p01 (plan) ---

Plan Title=Multiple Run
Short Identifier=Multiple
Geom File=g01
Flow File=f01
Subcritical Flow
K Sum by GR= 0
Std Step Tol= 0.01
Critical Tol= 0.01
Num of Std Step Trials= 20
Max Error Tol= 0.3
Flow Tol Ratio= 0.001
Split Flow NTrial= 30
Split Flow Tol= 0.02
Split Flow Ratio= 0.02
Log Output Level= 0
Friction Slope Method= 1
Unsteady Friction Slope Method= 2
Unsteady Bridges Friction Slope Method= 1
Parabolic Critical Depth
Global Vel Dist=  1 , 1 , 1
Global Log Level= 0
CheckData=True
Encroach Param= -1, 0, 0, 0
BEGIN DESCRIPTION:
Multiple Run
END DESCRIPTION:

--- Stream0325.f01 (steady flow) ---

Flow Title=Multiple
Program Version=4.10
Number of Profiles= 7
Profile Names=10-year,25-year,50-year,1pct_min,100-year,1pct_plu,500-year
River Rch & RM=Stream0325,Reach-1         ,1611
     441     715     963     631    1259    2512    2117
Boundary for River Rch & Prof#=Stream0325,Reach-1         , 1
Up Type= 0
Dn Type= 3
Dn Slope=0.02
Boundary for River Rch & Prof#=Stream0325,Reach-1         , 2
Up Type= 0
Dn Type= 3
Dn Slope=0.02
Boundary for River Rch & Prof#=Stream0325,Reach-1         , 3
Up Type= 0
Dn Type= 3
Dn Slope=0.02
Boundary for River Rch & Prof#=Stream0325,Reach-1         , 4
Up Type= 0
Dn Type= 3
Dn Slope=0.02
Boundary for River Rch & Prof#=Stream0325,Reach-1         , 5
Up Type= 0
Dn Type= 3
Dn Slope=0.02
Boundary for River Rch & Prof#=Stream0325,Reach-1         , 6
Up Type= 0
Dn Type= 3
Dn Slope=0.02
Boundary for River Rch & Prof#=Stream0325,Reach-1         , 7
Up Type= 0
Dn Type= 3
Dn Slope=0.02
DSS Import GetInterval= 0
DSS Import GetPeak= 0
DSS Import FillOption= 0

--- Stream0325.g01 (geometry) ---

Geom Title=Existing Conditions
Program Version=4.10

River Reach=Stream0325      ,Reach-1
Reach XY= 30
        1867825.       13927975.      1867824.54     13927894.54
      1867827.63     13927882.63      1867836.38     13927876.38
       1868140.2     13927874.51      1868169.15     13927877.06
       1868184.8     13927885.48      1868304.85     13928005.42
      1868330.89     13928023.04      1868374.99     13928025.85
      1868419.03     13928022.81      1868434.65     13928014.13
      1868476.75     13927978.34      1868495.21     13927974.64
      1868518.97     13927976.62      1868531.06     13927982.48
      1868545.09     13927994.42      1868661.36      13928111.8
      1868672.45     13928131.09      1868680.74     13928177.58
      1868697.81     13928198.97       1868722.3     13928219.64
      1868735.28     13928224.01      1868754.75     13928225.46
      1869090.21     13928224.51      1869119.16     13928227.05
       1869145.2     13928244.57      1869217.25     13928318.76
      1869224.41     13928336.83        1869225.       13928375.

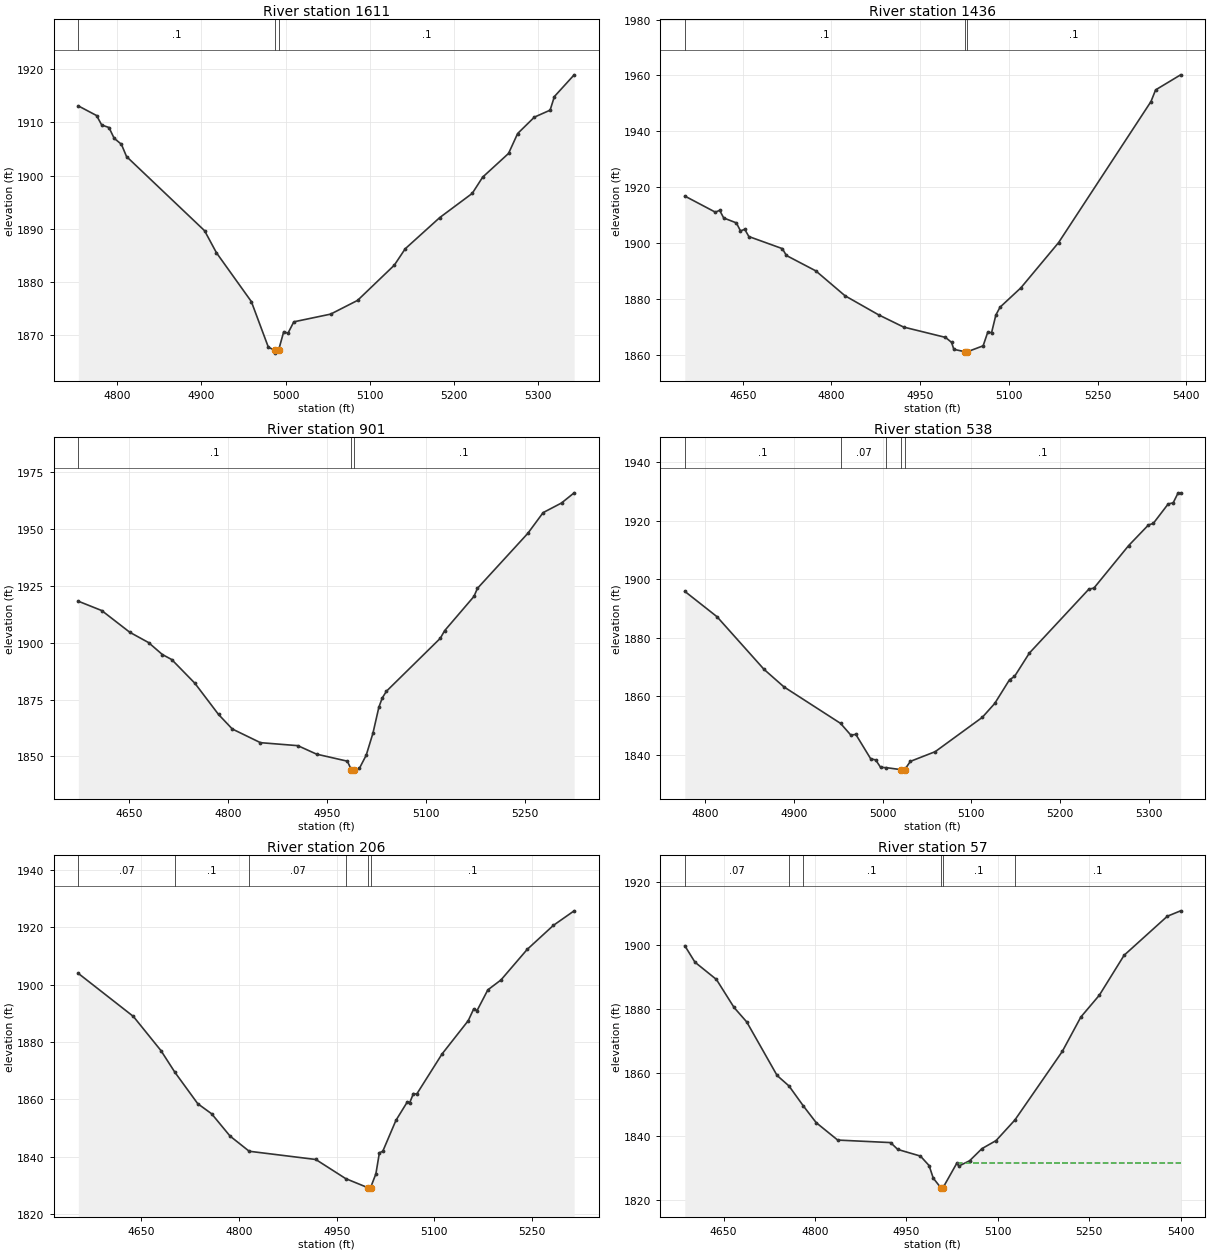
Type RM Length L Ch R = 1 ,1611    ,175,175,175
BEGIN DESCRIPTION:
Stream0325 4.0
END DESCRIPTION:
XS GIS Cut Line= 4
      1867787.04     13928087.14      1867891.18     13927941.34
      1867906.81     13927821.55      1867844.55      13927538.8
#Sta/Elev= 30
  4753.6 1913.08  4775.3 1911.27  4781.4 1909.49    4790 1909.02  4796.2    1907
  4804.8 1905.87  4810.9 1903.57  4903.7 1889.63  4917.8 1885.49  4959.3 1876.32
  4979.5 1867.75  4987.6 1867.13  4987.8 1866.63  4991.6 1867.13  4997.8 1870.66
  5002.8 1870.36  5009.8 1872.51  5053.6 1873.96  5085.6 1876.54  5129.3 1883.16
  5142.2 1886.23  5183.3  1892.1  5221.9 1896.64  5234.4 1899.71  5265.1 1904.15
  5275.9 1907.89  5295.8 1910.97  5314.5 1912.28  5319.6 1914.84  5343.1 1918.92
#Mann= 3 ,-1 , 0
  4753.6      .1       0  4987.6     .05       0  4991.6      .1       0
Bank Sta=4987.6,4991.6
XS Rating Curve= 0 ,0
Exp/Cntr=0.3,0.1

Type RM Length L Ch R = 1 ,1436    ,535,535,535
BEGIN DESCRIPTION:
Stream0325 3.0
END DESCRIPTION:
XS GIS Cut Line= 3
      1867765.42     13928198.52        1868075.       13927875.
      1868325.01     13927574.99
#Sta/Elev= 30
  4552.1  1916.8  4603.8 1911.02    4611 1911.69  4617.9 1908.94  4639.3 1907.18
  4646.2 1904.33  4653.5 1904.87  4660.4 1902.29    4717 1897.96  4723.9  1895.5
  4773.6 1889.99    4823 1881.07  4879.6 1874.26    4922 1869.86  4992.8 1866.16
  5003.1 1864.38    5007 1861.87  5025.9 1861.02  5026.1 1860.52  5029.9 1861.02
  5056.5 1863.14  5064.3 1868.01  5070.8 1867.87    5078 1874.16  5085.1 1876.98
  5120.3 1883.91  5184.1 1900.13  5340.3 1950.67  5348.1 1954.83  5390.4 1960.23
#Mann= 3 ,-1 , 0
  4552.1      .1       0  5025.9     .05       0  5029.9      .1       0
Bank Sta=5025.9,5029.9
XS Rating Curve= 0 ,0
Exp/Cntr=0.3,0.1

Type RM Length L Ch R = 1 ,901     ,363,363,363
BEGIN DESCRIPTION:
Stream0325 2.0
END DESCRIPTION:
XS GIS Cut Line= 3
      1868225.02     13928274.98      1868529.35     13928002.97
       1868600.2     13927666.22
#Sta/Elev= 30
  4572.6 1918.24  4608.1 1914.14  4650.7 1904.59  4679.1 1900.08  4700.1 1894.81
  4714.3 1892.61  4749.4  1882.2  4785.3 1868.48  4806.2 1862.09  4848.9 1856.08
  4905.7 1854.76  4934.1 1851.03  4980.8 1847.94    4987 1844.07  4987.2 1843.57
    4991 1844.07  4999.1 1844.82  5009.4 1850.58  5019.6 1860.24  5028.6 1871.66
  5033.7 1875.71    5040 1878.66  5121.8 1901.95  5128.3 1905.27  5172.9 1920.36
  5178.1 1923.88  5254.6 1948.07  5277.8 1957.18  5305.7 1961.41  5324.9 1965.88
#Mann= 3 ,-1 , 0
  4572.6      .1       0    4987     .05       0    4991      .1       0
Bank Sta=4987,4991
XS Rating Curve= 0 ,0
Exp/Cntr=0.3,0.1

Type RM Length L Ch R = 1 ,538     ,332,332,332
BEGIN DESCRIPTION:
Stream0325 1.0
END DESCRIPTION:
XS GIS Cut Line= 3
      1868675.01     13928424.98        1868775.       13928225.
        1868925.       13927925.
#Sta/Elev= 30
  4776.9 1895.86  4813.2 1887.18  4866.3 1869.13  4888.7 1863.15  4952.5 1850.66
  4964.1 1846.64  4969.7 1846.89  4986.5 1838.52  4992.1 1838.15  4997.7 1835.58
  5004.1  1835.5  5020.8 1834.81  5021.1 1834.31  5024.8 1834.81  5031.2 1837.65
  5059.2 1840.97  5112.3 1852.72  5126.3 1857.47    5143 1865.61  5148.6 1866.71
  5165.4 1874.74  5232.5 1896.63  5238.1 1896.96  5277.2  1911.5  5299.6 1918.58
  5305.1 1919.13  5321.9 1925.79  5327.5 1926.16  5333.1 1929.59  5335.9 1929.59
#Mann= 5 ,-1 , 0
  4776.9      .1       0  4952.5     .07       0  5004.1      .1       0
  5020.8     .05       0  5024.8      .1       0
Bank Sta=5020.8,5024.8
XS Rating Curve= 0 ,0
Exp/Cntr=0.3,0.1

Type RM Length L Ch R = 1 ,206     ,149,149,149
BEGIN DESCRIPTION:
Stream0325 0.0
END DESCRIPTION:
XS GIS Cut Line= 4
      1868834.19     13928563.77      1869085.12     13928318.81
      1869120.59     13928162.94      1869094.12     13927913.17
#Sta/Elev= 30
  4553.2 1903.95  4637.8 1888.93  4680.1 1877.03  4701.6 1869.44  4736.7 1858.49
    4758 1854.98  4786.3  1847.2  4815.7 1841.91    4918 1839.04    4964 1832.36
  4998.1  1829.2  4998.3  1828.7  5002.1  1829.2  5010.3 1834.02  5015.7 1841.38
  5020.9 1841.91  5041.1 1852.68  5058.8  1859.2  5062.4 1858.91    5068 1862.05
    5073 1861.84  5111.9 1875.83  5152.2 1887.47  5160.7 1891.61  5165.7 1890.97
  5182.3 1898.21  5202.4 1901.65  5242.7 1912.31  5282.9 1920.69  5314.9 1925.78
#Mann= 6 ,-1 , 0
  4553.2     .07       0  4701.6      .1       0  4815.7     .07       0
    4964      .1       0  4998.1     .05       0  5002.1      .1       0
Bank Sta=4998.1,5002.1
XS Rating Curve= 0 ,0
Exp/Cntr=0.3,0.1

Type RM Length L Ch R = 1 ,57      ,0,0,0
BEGIN DESCRIPTION:
Stream0325 0.1
END DESCRIPTION:
XS GIS Cut Line= 4
      1868899.02     13928581.95      1869177.64     13928363.22
      1869240.14     13928295.51      1869180.24      13927933.5
#Sta/Elev= 30
  4586.5 1899.86  4603.2 1894.68  4638.4 1889.25  4667.3 1880.45  4688.1  1875.9
  4737.9 1859.07  4757.4 1855.78  4780.8 1849.54    4802 1844.25  4837.3 1838.77
    4924 1837.98  4935.9 1835.82    4973 1833.74  4987.2 1830.76    4994 1826.82
  5006.2 1823.85  5006.4 1823.35  5010.2 1823.85  5032.8 1831.54  5036.1 1830.61
  5053.7 1832.27  5073.9 1836.08  5097.1 1838.61  5127.9 1845.07  5205.7 1866.63
  5236.1 1877.44  5266.5 1884.32  5307.1 1896.86    5378 1909.13  5399.8 1910.83
#Mann= 6 ,-1 , 0
  4586.5     .07       0  4757.4      .1       0  4780.8      .1       0
  5006.2     .05       0  5010.2      .1       0  5127.9      .1       0
#XS Ineff= 2 , 0
                         5032.83         1831.54
Permanent Ineff=
       F       F
Bank Sta=5006.2,5010.2
XS Rating Curve= 0 ,0
Exp/Cntr=0.3,0.1

Chan Stop Cuts=-1
Use User Specified Reach Order=0
Composite Channel Slope=5