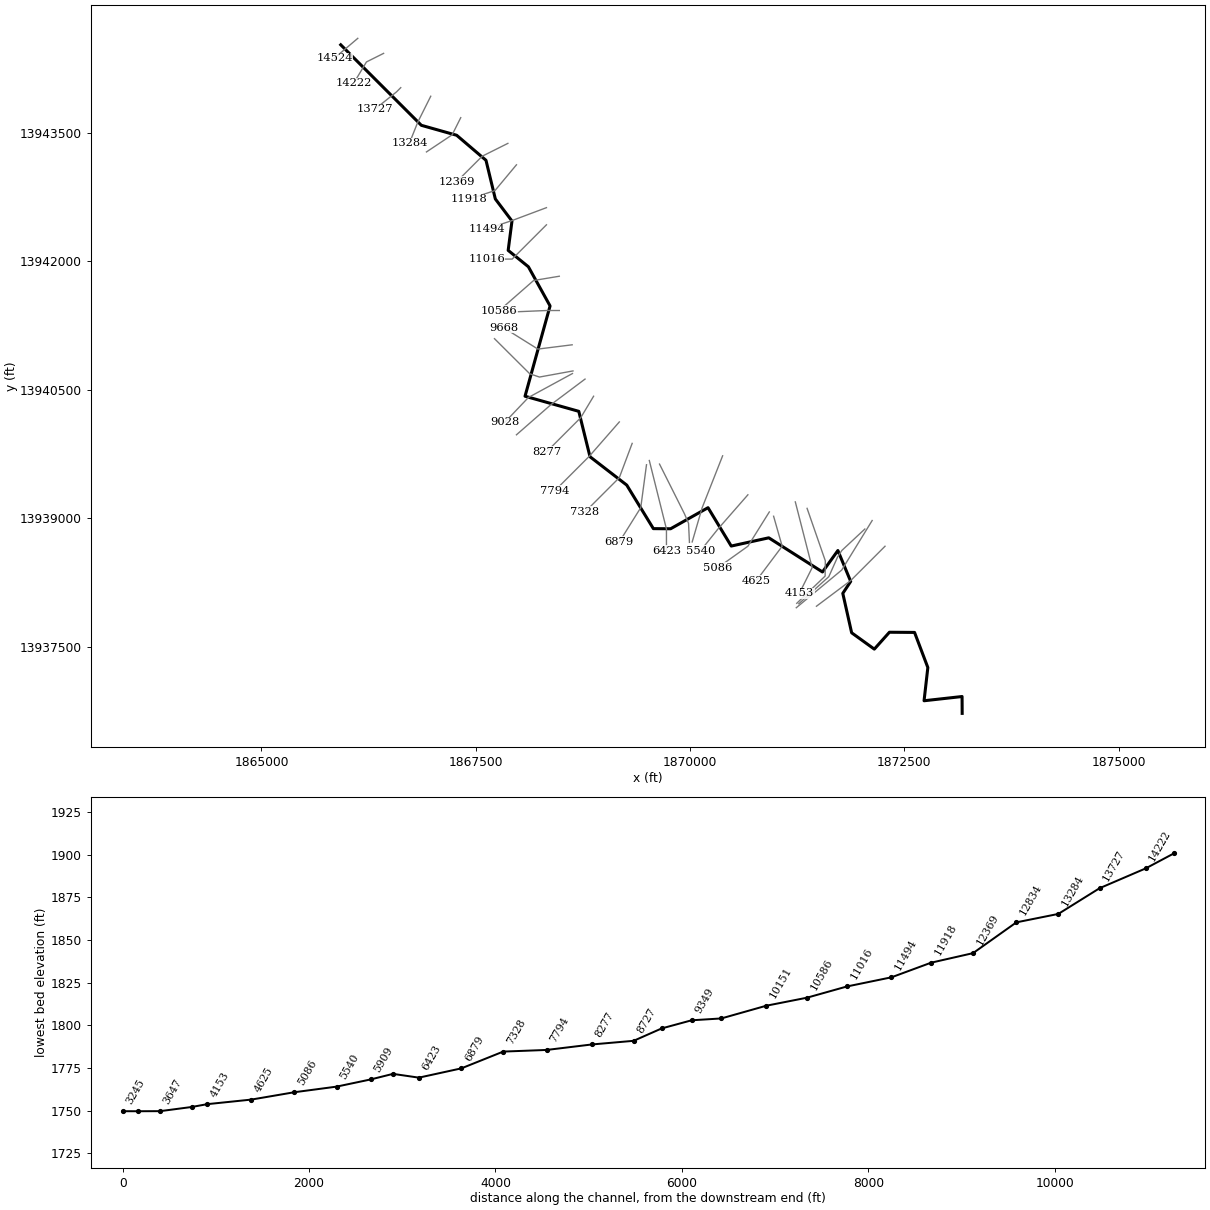
--- Stream0326.prj (project) ---

Proj Title=Stream0326 Base Level Engineering
Current Plan=p01
Default Exp/Contr=0.3,0.1
English Units
Geom File=g01
Flow File=f01
Plan File=p01
BEGIN DESCRIPTION:
Stream0326
END DESCRIPTION:

--- Stream0326.p01 (plan) ---

Plan Title=Multiple Run
Short Identifier=Multiple
Geom File=g01
Flow File=f01
Subcritical Flow
K Sum by GR= 0
Std Step Tol= 0.01
Critical Tol= 0.01
Num of Std Step Trials= 20
Max Error Tol= 0.3
Flow Tol Ratio= 0.001
Split Flow NTrial= 30
Split Flow Tol= 0.02
Split Flow Ratio= 0.02
Log Output Level= 0
Friction Slope Method= 1
Unsteady Friction Slope Method= 2
Unsteady Bridges Friction Slope Method= 1
Parabolic Critical Depth
Global Vel Dist=  1 , 1 , 1
Global Log Level= 0
CheckData=True
Encroach Param= -1, 0, 0, 0
BEGIN DESCRIPTION:
Multiple Run
END DESCRIPTION:

--- Stream0326.f01 (steady flow) ---

Flow Title=Multiple
Number of Profiles=7
Profile Names=10-year,25-year,50-year,1pct_min,100-year,1pct_plu,500-year
River Rch & RM= Stream0326,Reach-1,14524
     894    1518    2111    1422    2837    5660    5055
River Rch & RM= Stream0326,Reach-1,12369
    1646    2895    4120    2833    5652   11277   10513
River Rch & RM= Stream0326,Reach-1,9028
    2052    3644    5218    3606    7195   14356   13524
River Rch & RM= Stream0326,Reach-1,5909
    2243    3995    5731    3965    7912   15786   14912
River Rch & RM= Stream0326,Reach-1,3647
    2704    4855    7002    4867    9711   19375   18474
Boundary for River Rch & Prof#=Stream0326,Reach-1,1
Up Type=0
Dn Type=3
Dn Slope=0.005
Boundary for River Rch & Prof#=Stream0326,Reach-1,2
Up Type=0
Dn Type=3
Dn Slope=0.005
Boundary for River Rch & Prof#=Stream0326,Reach-1,3
Up Type=0
Dn Type=3
Dn Slope=0.005
Boundary for River Rch & Prof#=Stream0326,Reach-1,4
Up Type=0
Dn Type=3
Dn Slope=0.005
Boundary for River Rch & Prof#=Stream0326,Reach-1,5
Up Type=0
Dn Type=3
Dn Slope=0.005
Boundary for River Rch & Prof#=Stream0326,Reach-1,6
Up Type=0
Dn Type=3
Dn Slope=0.005
Boundary for River Rch & Prof#=Stream0326,Reach-1,7
Up Type=0
Dn Type=3
Dn Slope=0.005

--- Stream0326.g01 (geometry) ---

Geom Title=Existing Conditions

River Reach=Stream0326,Reach-1
Reach XY= 30
      1865925.00     13944525.00      1866865.32     13943585.76
      1867277.47     13943469.54      1867619.54     13943177.45
      1867728.61     13942726.50      1867922.76     13942469.07
      1867878.34     13942126.72      1868114.24     13941935.39
      1868367.21     13941478.42      1868075.00     13940425.00
      1868702.15     13940248.85      1868833.13     13939718.93
      1869261.60     13939388.30      1869572.26     13938880.34
      1869773.45     13938878.75      1870210.02     13939124.75
      1870480.85     13938677.06      1870918.89     13938773.21
      1871545.28     13938374.61      1871725.00     13938625.00
      1871874.45     13938264.36      1871782.30     13938125.08
      1871885.52     13937665.21      1872150.04     13937474.49
      1872326.25     13937671.55      1872619.38     13937669.44
      1872774.48     13937259.78      1872730.34     13936872.26
      1873173.81     13936921.56      1873175.00     13936725.00

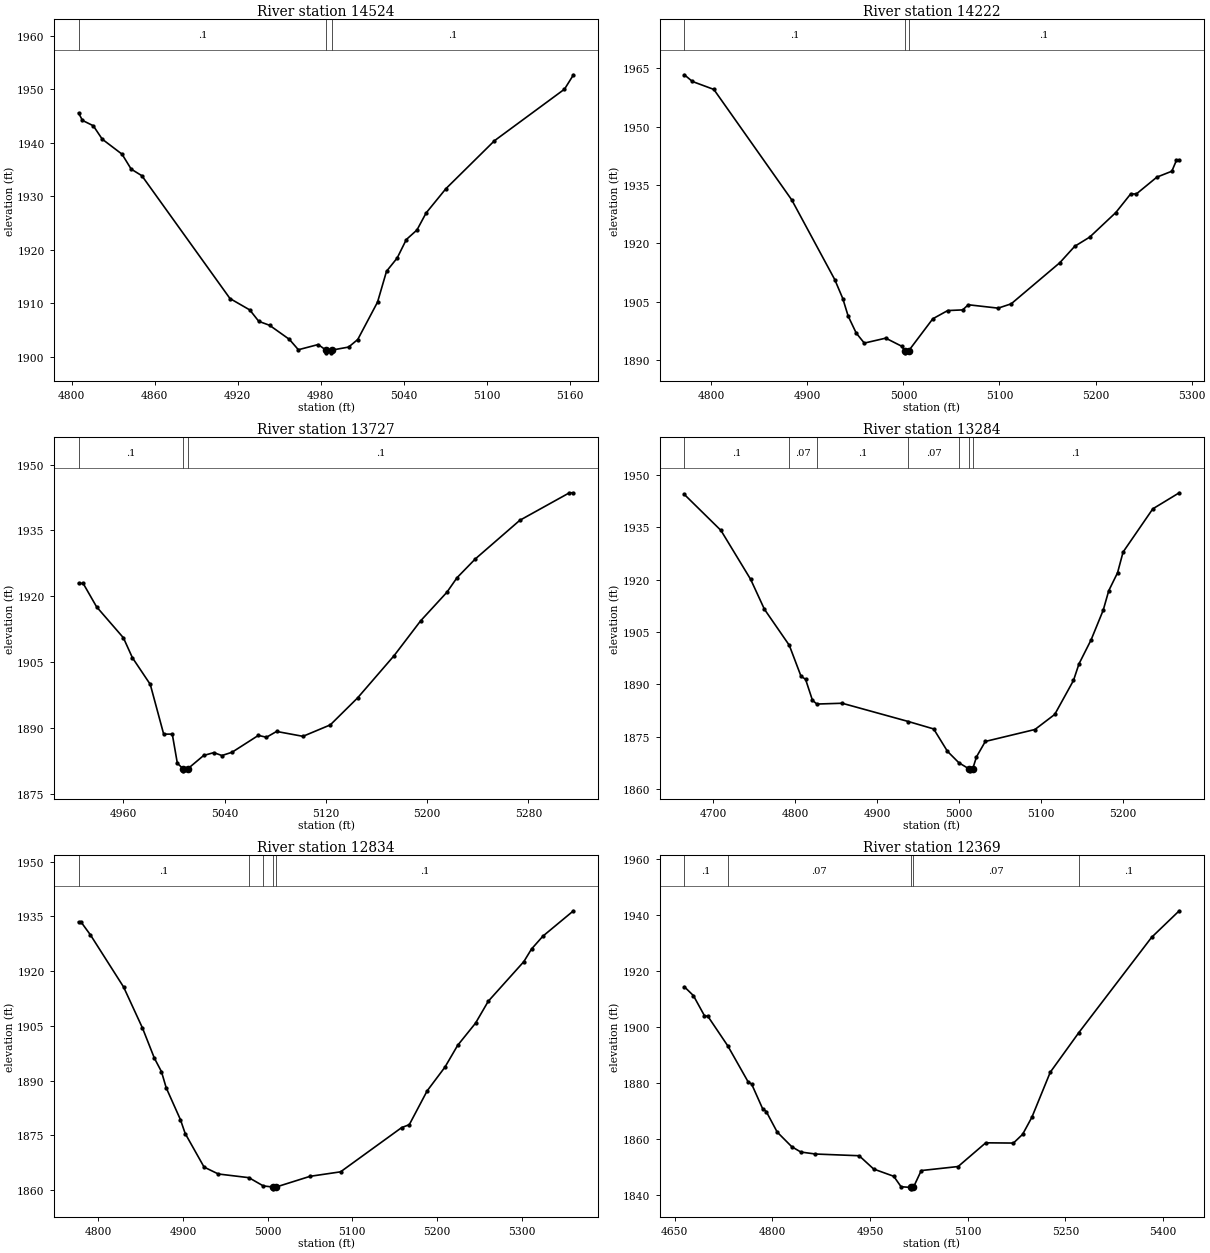
Type RM Length L Ch R = 1,14524,302,302,302
BEGIN DESCRIPTION:
Stream0326 30.0
END DESCRIPTION:
XS GIS Cut Line= 2
      1866123.86     13944600.40      1865851.16     13944369.07
#Sta/Elev= 30
  4805.1 1945.53  4807.9 1944.16  4815.7 1943.16  4822.2 1940.65  4836.5 1937.84
  4843.1 1935.05  4850.8 1933.82  4914.5 1910.85  4928.8 1908.72  4935.3 1906.59
  4943.1 1905.85  4957.4 1903.22  4963.9 1901.28  4978.2 1902.25  4983.9 1901.20
  4984.2 1900.70  4987.7 1900.70  4987.9 1901.20  5000.2 1901.78  5006.8 1903.19
  5021.1 1910.18  5027.6 1915.95  5035.3 1918.43  5041.9 1921.88  5049.6 1923.67
  5056.2 1926.85  5070.5 1931.39  5105.6 1940.36  5156.2 1950.00  5162.7 1952.69
#Mann=3,-1,0
  4805.1     0.1       0  4983.9    0.05       0  4987.9     0.1       0
Bank Sta=4983.9,4987.9
Exp/Cntr=0.3,0.1

Type RM Length L Ch R = 1,14222,495,495,495
BEGIN DESCRIPTION:
Stream0326 29.0
END DESCRIPTION:
XS GIS Cut Line= 3
      1866424.99     13944425.00      1866225.00     13944325.00
      1866075.02     13944075.04
#Sta/Elev= 30
  4772.0 1963.29  4780.4 1961.57  4802.7 1959.53  4883.8 1931.17  4928.5 1910.75
  4936.9 1905.87  4942.5 1901.36  4950.9 1897.00  4959.3 1894.43  4981.6 1895.70
  4998.5 1893.59  5001.4 1892.43  5001.6 1891.93  5005.4 1892.43  5030.6 1900.67
  5046.1 1902.78  5061.7 1902.95  5067.5 1904.27  5098.6 1903.40  5112.2 1904.51
  5162.8 1915.06  5178.3 1919.27  5193.9 1921.63  5221.1 1927.94  5236.6 1932.73
  5242.4 1932.69  5263.8 1937.02  5279.4 1938.54  5284.2 1941.35  5287.1 1941.35
#Mann=3,-1,0
  4772.0     0.1       0  5001.4    0.05       0  5005.4     0.1       0
Bank Sta=5001.4,5005.4
Exp/Cntr=0.3,0.1

Type RM Length L Ch R = 1,13727,443,443,443
BEGIN DESCRIPTION:
Stream0326 28.0
END DESCRIPTION:
XS GIS Cut Line= 3
      1866625.03     13944025.03      1866575.00     13943975.00
      1866325.01     13943775.01
#Sta/Elev= 30
  4924.7 1922.96  4928.3 1922.96  4938.9 1917.63  4960.1 1910.58  4967.2 1906.05
  4981.3 1899.99  4991.9 1888.67  4998.7 1888.67  5002.7 1882.05  5007.1 1880.82
  5007.3 1880.32  5011.1 1880.82  5023.5 1883.82  5031.5 1884.46  5037.9 1883.80
  5045.9 1884.55  5066.7 1888.38  5073.1 1887.96  5081.1 1889.28  5101.9 1888.17
  5123.5 1890.77  5145.1 1896.92  5173.9 1906.52  5194.8 1914.42  5215.6 1920.94
  5223.6 1924.25  5238.0 1928.51  5273.2 1937.31  5312.4 1943.57  5315.6 1943.57
#Mann=3,-1,0
  4924.7     0.1       0  5007.1    0.05       0  5011.1     0.1       0
Bank Sta=5007.1,5011.1
Exp/Cntr=0.3,0.1

Type RM Length L Ch R = 1,13284,450,450,450
BEGIN DESCRIPTION:
Stream0326 27.0
END DESCRIPTION:
XS GIS Cut Line= 3
      1866974.98     13943924.96      1866825.00     13943625.00
      1866725.01     13943375.02
#Sta/Elev= 30
  4664.4 1944.42  4709.1 1934.12  4745.4 1920.10  4762.2 1911.55  4792.6 1901.22
  4806.9 1892.37  4812.5 1891.47  4820.9 1885.47  4826.3 1884.39  4857.2 1884.62
  4938.0 1879.39  4969.0 1877.26  4985.8 1870.86  4999.8 1867.57  5012.6 1865.76
  5012.8 1865.26  5016.6 1865.76  5021.3 1869.27  5032.1 1873.68  5092.7 1877.10
  5116.9 1881.42  5139.8 1891.15  5146.5 1895.89  5161.3 1902.77  5176.1 1911.26
  5182.9 1916.87  5193.6 1921.97  5200.4 1927.93  5236.7 1940.30  5269.0 1944.90
#Mann=7,-1,0
  4664.4     0.1       0  4792.6    0.07       0  4826.3     0.1       0
  4938.0    0.07       0  4999.8     0.1       0  5012.6    0.05       0
  5016.6     0.1       0
Bank Sta=5012.6,5016.6
Exp/Cntr=0.3,0.1

Type RM Length L Ch R = 1,12834,465,465,465
BEGIN DESCRIPTION:
Stream0326 26.0
END DESCRIPTION:
XS GIS Cut Line= 3
      1867324.99     13943674.98      1867225.00     13943475.00
      1866925.03     13943275.02
#Sta/Elev= 30
  4776.9 1933.46  4779.7 1933.46  4790.9 1929.89  4830.0 1915.63  4852.3 1904.39
  4866.3 1896.15  4874.7 1892.44  4880.3 1888.01  4897.1 1879.28  4902.7 1875.49
  4925.0 1866.29  4941.8 1864.40  4977.9 1863.39  4994.9 1861.13  5006.0 1860.83
  5006.2 1860.33  5010.0 1860.83  5050.1 1863.76  5086.1 1864.99  5158.2 1877.11
  5167.2 1877.91  5188.3 1887.18  5209.3 1893.68  5224.3 1899.65  5245.4 1905.73
  5260.4 1911.72  5302.4 1922.58  5311.5 1926.05  5325.0 1929.58  5361.0 1936.51
#Mann=5,-1,0
  4776.9     0.1       0  4977.9    0.07       0  4994.9     0.1       0
  5006.0    0.05       0  5010.0     0.1       0
Bank Sta=5006,5010
Exp/Cntr=0.3,0.1

Type RM Length L Ch R = 1,12369,451,451,451
BEGIN DESCRIPTION:
Stream0326 25.0
END DESCRIPTION:
XS GIS Cut Line= 3
      1867874.96     13943374.98      1867575.00     13943225.00
      1867275.02     13942925.02
#Sta/Elev= 30
  4665.0 1914.39  4678.9 1911.24  4695.7 1904.13  4701.3 1903.79  4731.6 1893.33
  4762.8 1880.50  4768.4 1879.62  4785.1 1870.91  4790.7 1869.89  4807.5 1862.55
  4829.9 1857.32  4843.8 1855.43  4866.2 1854.72  4933.3 1854.11  4955.6 1849.36
  4986.4 1846.78  4997.6 1843.06  5012.5 1842.80  5012.8 1842.30  5016.5 1842.80
  5028.6 1848.82  5085.2 1850.26  5127.6 1858.72  5170.1 1858.63  5184.2 1861.75
  5198.4 1867.83  5226.6 1883.89  5270.3 1897.98  5382.2 1932.03  5424.6 1941.50
#Mann=5,-1,0
  4665.0     0.1       0  4731.6    0.07       0  5012.5    0.05       0
  5016.5    0.07       0  5270.3     0.1       0
Bank Sta=5012.5,5016.5
Exp/Cntr=0.3,0.1

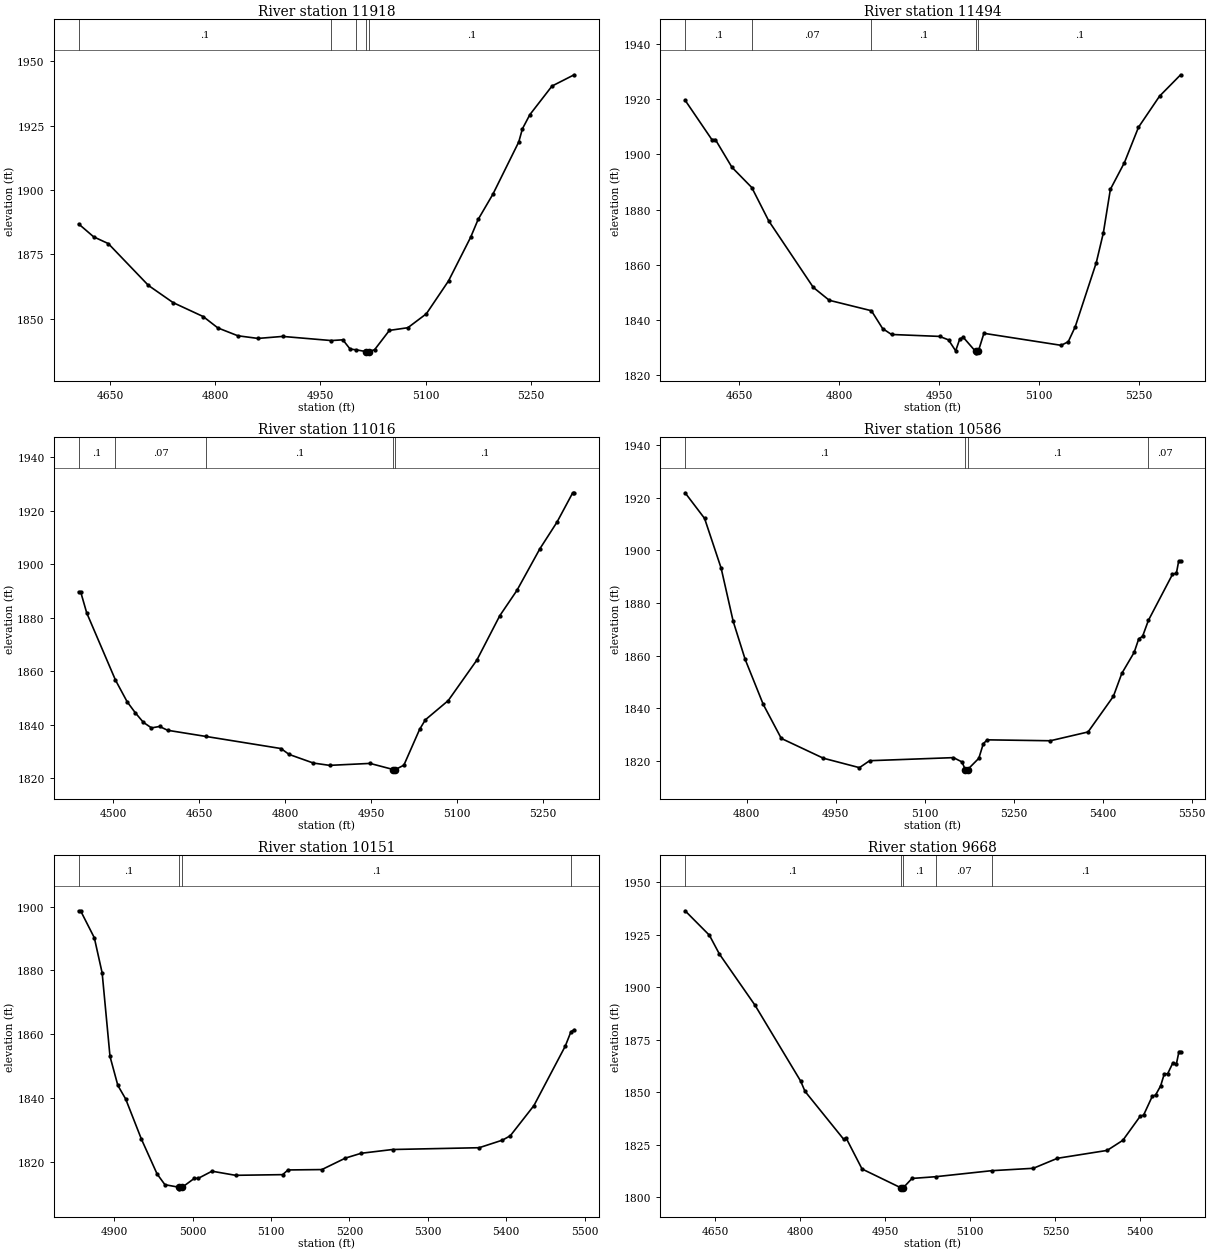
Type RM Length L Ch R = 1,11918,424,424,424
BEGIN DESCRIPTION:
Stream0326 24.0
END DESCRIPTION:
XS GIS Cut Line= 3
      1867974.99     13943124.98      1867725.00     13942825.00
      1867425.02     13942725.01
#Sta/Elev= 30
  4605.3 1886.78  4626.8 1881.75  4647.6 1879.14  4704.9 1862.87  4740.0 1856.21
  4783.0 1850.78  4803.8 1846.38  4832.4 1843.32  4861.1 1842.29  4896.2 1843.07
  4965.7 1841.46  4982.1 1841.75  4992.5 1838.15  5001.2 1837.86  5014.9 1837.19
  5015.1 1836.69  5018.9 1837.19  5027.4 1837.91  5048.5 1845.41  5074.8 1846.45
  5101.2 1851.86  5132.8 1864.63  5164.4 1881.61  5175.0 1888.50  5196.1 1898.33
  5233.0 1918.64  5238.2 1923.74  5248.8 1929.23  5280.4 1940.35  5312.0 1944.73
#Mann=5,-1,0
  4605.3     0.1       0  4965.7    0.07       0  5001.2     0.1       0
  5014.9    0.05       0  5018.9     0.1       0
Bank Sta=5014.9,5018.9
Exp/Cntr=0.3,0.1

Type RM Length L Ch R = 1,11494,478,478,478
BEGIN DESCRIPTION:
Stream0326 23.0
END DESCRIPTION:
XS GIS Cut Line= 3
      1868325.01     13942625.00      1867925.00     13942475.00
      1867625.04     13942375.01
#Sta/Elev= 30
  4568.7 1919.64  4608.8 1905.40  4614.1 1905.40  4639.0 1895.35  4668.8 1888.00
  4694.2 1875.93  4761.0 1851.86  4785.0 1847.18  4848.2 1843.40  4865.1 1836.92
  4878.4 1834.80  4950.5 1834.10  4963.9 1832.84  4974.6 1828.87  4980.8 1833.20
  4986.1 1833.76  5004.5 1828.65  5004.7 1828.15  5008.5 1828.65  5017.0 1835.22
  5132.9 1830.87  5143.5 1832.17  5154.0 1837.61  5185.6 1860.84  5196.2 1871.62
  5206.7 1887.36  5227.8 1897.05  5248.9 1909.85  5280.5 1921.11  5312.1 1928.85
#Mann=5,-1,0
  4568.7     0.1       0  4668.8    0.07       0  4848.2     0.1       0
  5004.5    0.05       0  5008.5     0.1       0
Bank Sta=5004.5,5008.5
Exp/Cntr=0.3,0.1

Type RM Length L Ch R = 1,11016,430,430,430
BEGIN DESCRIPTION:
Stream0326 22.0
END DESCRIPTION:
XS GIS Cut Line= 3
      1868324.98     13942424.98      1867925.00     13942025.00
      1867624.96     13942025.00
#Sta/Elev= 30
  4439.1 1889.78  4442.6 1889.78  4453.2 1881.87  4503.5 1856.71  4523.9 1848.60
  4538.1 1844.50  4552.2 1840.92  4566.4 1838.84  4580.5 1839.38  4594.6 1837.95
  4661.7 1835.64  4792.6 1831.12  4806.8 1828.92  4849.2 1825.69  4877.5 1824.83
  4948.2 1825.56  4988.6 1823.28  4988.9 1822.78  4992.6 1823.28  5007.3 1824.90
  5034.8 1838.29  5044.8 1841.86  5084.8 1849.06  5134.8 1864.21  5174.8 1880.79
  5204.8 1890.27  5244.8 1905.81  5274.8 1915.81  5302.3 1926.79  5304.8 1926.79
#Mann=5,-1,0
  4439.1     0.1       0  4503.5    0.07       0  4661.7     0.1       0
  4988.6    0.05       0  4992.6     0.1       0
Bank Sta=4988.6,4992.6
Exp/Cntr=0.3,0.1

Type RM Length L Ch R = 1,10586,435,435,435
BEGIN DESCRIPTION:
Stream0326 21.0
END DESCRIPTION:
XS GIS Cut Line= 3
      1868474.96     13941824.99      1868175.00     13941775.00
      1867775.01     13941425.00
#Sta/Elev= 30
  4695.9 1921.84  4728.8 1912.08  4756.7 1893.19  4777.0 1873.00  4797.2 1858.54
  4827.7 1841.43  4858.1 1828.51  4929.0 1820.99  4989.9 1817.40  5007.1 1820.04
  5148.5 1821.21  5162.8 1819.57  5168.3 1816.69  5168.6 1816.19  5172.4 1816.69
  5191.2 1820.95  5198.8 1826.52  5205.5 1827.97  5311.8 1827.62  5375.4 1830.96
  5418.1 1844.49  5432.3 1853.20  5453.2 1861.22  5460.8 1866.30  5467.4 1867.33
  5477.2 1873.38  5517.7 1890.81  5524.4 1891.31  5528.2 1895.84  5531.5 1895.84
#Mann=4,-1,0
  4695.9     0.1       0  5168.3    0.05       0  5172.4     0.1       0
  5477.2    0.07       0
Bank Sta=5168.3,5172.4
Exp/Cntr=0.3,0.1

Type RM Length L Ch R = 1,10151,483,483,483
BEGIN DESCRIPTION:
Stream0326 20.0
END DESCRIPTION:
XS GIS Cut Line= 3
      1868474.98     13941425.00      1868325.00     13941425.00
      1867843.71     13941404.70
#Sta/Elev= 30
  4854.8 1898.67  4857.3 1898.67  4874.8 1890.21  4884.8 1879.17  4894.8 1853.00
  4904.8 1843.92  4914.8 1839.66  4934.8 1827.11  4954.8 1816.18  4964.8 1812.81
  4982.7 1812.01  4983.0 1811.51  4986.9 1812.01  5002.3 1814.80  5007.3 1814.80
  5024.8 1817.04  5054.8 1815.75  5114.9 1815.96  5121.7 1817.43  5164.9 1817.55
  5194.9 1821.15  5215.0 1822.66  5255.0 1823.84  5365.4 1824.40  5395.1 1826.78
  5405.1 1828.15  5435.2 1837.61  5475.2 1856.27  5482.4 1860.76  5486.5 1861.38
#Mann=4,-1,0
  4854.8     0.1       0  4982.7    0.05       0  4986.9     0.1       0
  5482.4    0.07       0
Bank Sta=4982.7,4986.9
Exp/Cntr=0.3,0.1

Type RM Length L Ch R = 1,9668,319,319,319
BEGIN DESCRIPTION:
Stream0326 19.0
END DESCRIPTION:
XS GIS Cut Line= 3
      1868625.04     13941025.00      1868225.00     13940975.00
      1867825.04     13941224.97
#Sta/Elev= 30
  4596.4 1936.40  4639.3 1924.76  4656.9 1915.84  4719.9 1891.42  4800.5 1855.30
  4808.1 1850.46  4876.1 1827.74  4881.1 1828.02  4908.8 1813.51  4977.3 1804.56
  4977.5 1804.06  4981.5 1804.56  4997.0 1809.01  5038.7 1809.83  5137.6 1812.70
  5211.2 1813.84  5253.7 1818.60  5341.5 1822.35  5369.2 1827.16  5399.9 1838.64
  5405.8 1839.14  5421.1 1848.07  5427.0 1848.73  5435.9 1853.05  5442.4 1858.82
  5448.3 1858.84  5457.7 1864.12  5463.6 1863.37  5468.3 1869.39  5471.2 1869.39
#Mann=5,-1,0
  4596.4     0.1       0  4977.3    0.05       0  4981.5     0.1       0
  5038.7    0.07       0  5137.6     0.1       0
Bank Sta=4977.3,4981.5
Exp/Cntr=0.3,0.1

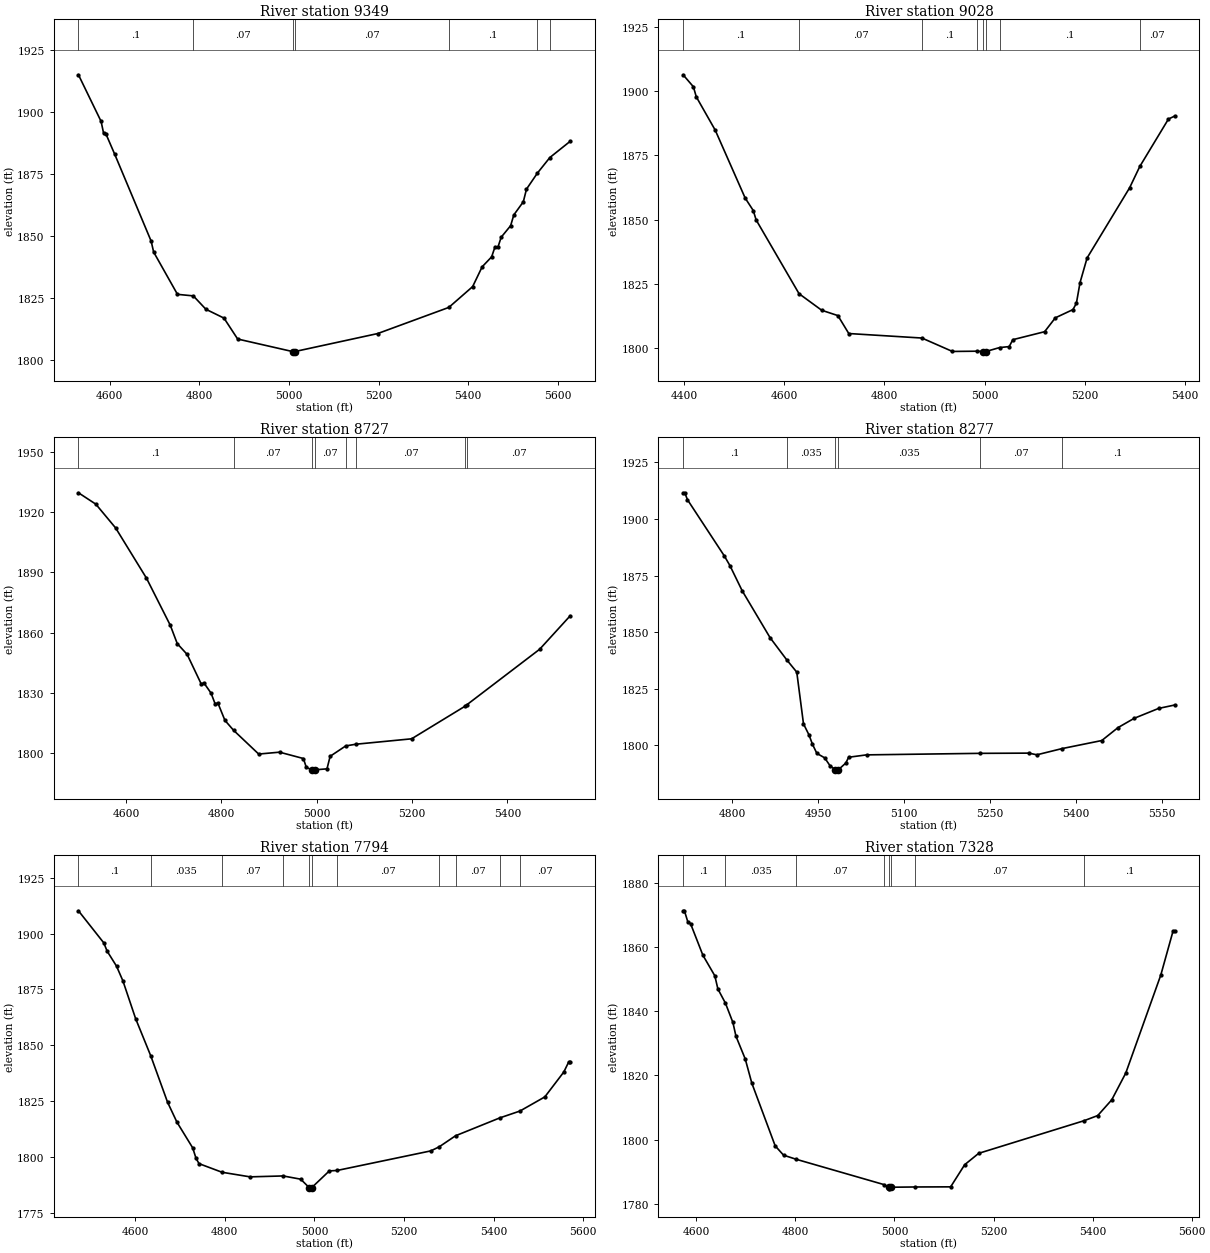
Type RM Length L Ch R = 1,9349,321,321,321
BEGIN DESCRIPTION:
Stream0326 18.0
END DESCRIPTION:
XS GIS Cut Line= 4
      1868634.75     13940720.19      1868243.06     13940648.75
      1868129.71     13940687.29      1867718.64     13941096.51
#Sta/Elev= 30
  4530.0 1914.92  4580.6 1896.14  4586.2 1891.35  4591.3 1891.13  4611.1 1882.88
  4692.4 1847.92  4697.9 1843.55  4751.1 1826.52  4786.5 1825.90  4814.6 1820.51
  4855.0 1816.95  4885.5 1808.53  5008.5 1803.47  5008.7 1802.97  5012.7 1803.47
  5198.1 1810.73  5357.0 1821.26  5410.2 1829.64  5431.4 1837.61  5452.6 1841.62
  5459.7 1845.42  5466.8 1845.61  5473.9 1849.52  5495.0 1854.16  5502.1 1858.50
  5523.3 1863.78  5530.4 1868.88  5554.8 1875.34  5582.6 1881.61  5627.9 1888.13
#Mann=7,-1,0
  4530.0     0.1       0  4786.5    0.07       0  5008.5    0.05       0
  5012.7    0.07       0  5357.0     0.1       0  5554.8    0.07       0
  5582.6     0.1       0
Bank Sta=5008.5,5012.7
Exp/Cntr=0.3,0.1

Type RM Length L Ch R = 1,9028,301,301,301
BEGIN DESCRIPTION:
Stream0326 17.1
END DESCRIPTION:
XS GIS Cut Line= 3
      1868628.22     13940689.76      1868114.36     13940410.26
      1867840.07     13940122.08
#Sta/Elev= 30
  4397.5 1906.38  4418.1 1901.72  4423.9 1897.80  4461.8 1884.82  4521.6 1858.42
  4537.8 1853.56  4543.5 1849.92  4629.3 1821.21  4674.6 1814.77  4706.9 1812.70
  4728.7 1805.72  4874.8 1803.97  4935.8 1798.75  4985.8 1798.85  4997.5 1798.71
  4997.8 1798.21  5002.4 1798.71  5030.1 1800.26  5049.3 1800.64  5056.6 1803.33
  5120.1 1806.43  5141.5 1811.83  5176.7 1815.03  5183.6 1817.48  5190.9 1825.54
  5205.0 1835.12  5290.0 1862.42  5310.3 1870.70  5367.6 1889.16  5380.3 1890.34
#Mann=8,-1,0
  4397.5     0.1       0  4629.3    0.07       0  4874.8     0.1       0
  4985.8    0.07       0  4997.5    0.05       0  5002.4    0.07       0
  5030.1     0.1       0  5310.3    0.07       0
Bank Sta=4997.5,5002.4
Exp/Cntr=0.3,0.1

Type RM Length L Ch R = 1,8727,450,450,450
BEGIN DESCRIPTION:
Stream0326 17.0
END DESCRIPTION:
XS GIS Cut Line= 3
      1868775.02     13940625.01      1868375.00     13940325.00
      1867975.02     13939975.02
#Sta/Elev= 30
  4500.1 1929.78  4536.6 1924.09  4578.2 1912.19  4642.8 1887.16  4692.8 1863.61
  4707.4 1854.47  4728.2 1849.05  4757.4 1834.45  4763.7 1834.72  4778.2 1829.78
  4786.6 1824.54  4792.8 1824.69  4807.4 1816.15  4825.5 1811.20  4878.2 1799.33
  4922.0 1800.27  4972.0 1797.10  4978.2 1792.63  4990.3 1791.45  4990.7 1790.95
  4995.3 1791.45  5021.5 1791.94  5028.1 1798.21  5060.8 1803.39  5082.1 1804.24
  5199.0 1806.94  5311.0 1823.20  5314.7 1823.90  5467.6 1851.65  5531.6 1868.34
#Mann=8,-1,0
  4500.1     0.1       0  4825.5    0.07       0  4990.3    0.05       0
  4995.3    0.07       0  5060.8   0.035       0  5082.1    0.07       0
  5311.0     0.1       0  5314.7    0.07       0
Bank Sta=4990.3,4995.3
Exp/Cntr=0.3,0.1

Type RM Length L Ch R = 1,8277,483,483,483
BEGIN DESCRIPTION:
Stream0326 16.0
END DESCRIPTION:
XS GIS Cut Line= 3
      1868874.98     13940424.97      1868725.00     13940175.00
      1868325.00     13939775.00
#Sta/Elev= 30
  4714.5 1911.57  4717.4 1911.57  4722.2 1908.48  4786.4 1883.69  4796.1 1879.45
  4817.5 1868.32  4866.1 1847.62  4895.0 1837.88  4912.7 1832.38  4924.4 1809.56
  4934.1 1804.61  4939.9 1800.63  4947.7 1796.52  4961.3 1794.55  4971.0 1790.94
  4980.2 1789.31  4980.6 1788.81  4985.2 1789.31  4998.2 1792.25  5003.1 1794.81
  5034.3 1795.86  5231.4 1796.53  5317.1 1796.63  5331.3 1795.89  5374.6 1798.60
  5444.4 1802.19  5472.7 1807.90  5501.0 1812.01  5543.4 1816.36  5571.7 1817.88
#Mann=6,-1,0
  4714.5     0.1       0  4895.0   0.035       0  4980.2   0.035       0
  4985.2   0.035       0  5231.4    0.07       0  5374.6     0.1       0
Bank Sta=4980.2,4985.2
Exp/Cntr=0.3,0.1

Type RM Length L Ch R = 1,7794,466,466,466
BEGIN DESCRIPTION:
Stream0326 15.0
END DESCRIPTION:
XS GIS Cut Line= 3
      1869175.02     13940125.02      1868825.00     13939725.00
      1868425.02     13939325.02
#Sta/Elev= 30
  4473.4 1910.23  4529.9 1895.86  4537.5 1892.11  4558.4 1885.41  4572.6 1878.83
  4601.1 1861.84  4634.7 1845.25  4672.3 1824.41  4693.2 1815.49  4728.3 1803.99
  4735.9 1799.23  4742.5 1796.90  4793.8 1793.04  4856.4 1790.98  4930.0 1791.39
  4969.3 1789.94  4988.6 1786.11  4989.0 1785.61  4993.7 1786.11  5033.2 1793.64
  5050.7 1793.85  5259.5 1802.61  5278.4 1804.44  5314.8 1809.39  5413.4 1817.39
  5458.5 1820.47  5514.1 1826.82  5556.5 1837.99  5567.1 1842.37  5570.6 1842.37
#Mann=11,-1,0
  4473.4     0.1       0  4634.7   0.035       0  4793.8    0.07       0
  4930.0     0.1       0  4988.6    0.05       0  4993.7     0.1       0
  5050.7    0.07       0  5278.4     0.1       0  5314.8    0.07       0
  5413.4     0.1       0  5458.5    0.07       0
Bank Sta=4988.6,4993.7
Exp/Cntr=0.3,0.1

Type RM Length L Ch R = 1,7328,449,449,449
BEGIN DESCRIPTION:
Stream0326 14.0
END DESCRIPTION:
XS GIS Cut Line= 3
      1869325.00     13939874.99      1869175.00     13939475.00
      1868774.98     13939074.98
#Sta/Elev= 30
  4573.1 1871.21  4575.8 1871.21  4582.9 1867.64  4588.2 1867.20  4613.1 1857.37
  4637.2 1850.97  4643.4 1846.86  4658.6 1842.46  4673.7 1836.44  4679.9 1832.15
  4698.6 1825.08  4711.9 1817.55  4759.1 1798.02  4776.0 1795.13  4801.3 1793.86
  4979.2 1785.95  4988.0 1785.15  4988.3 1784.65  4993.1 1785.15  5041.3 1785.23
  5113.4 1785.27  5141.7 1792.16  5170.0 1795.70  5382.6 1805.85  5410.4 1807.46
  5438.7 1812.36  5467.0 1820.69  5537.7 1851.19  5562.4 1864.86  5566.0 1864.86
#Mann=8,-1,0
  4573.1     0.1       0  4658.6   0.035       0  4801.3    0.07       0
  4979.2     0.1       0  4988.0    0.05       0  4993.1     0.1       0
  5041.3    0.07       0  5382.6     0.1       0
Bank Sta=4988,4993.1
Exp/Cntr=0.3,0.1

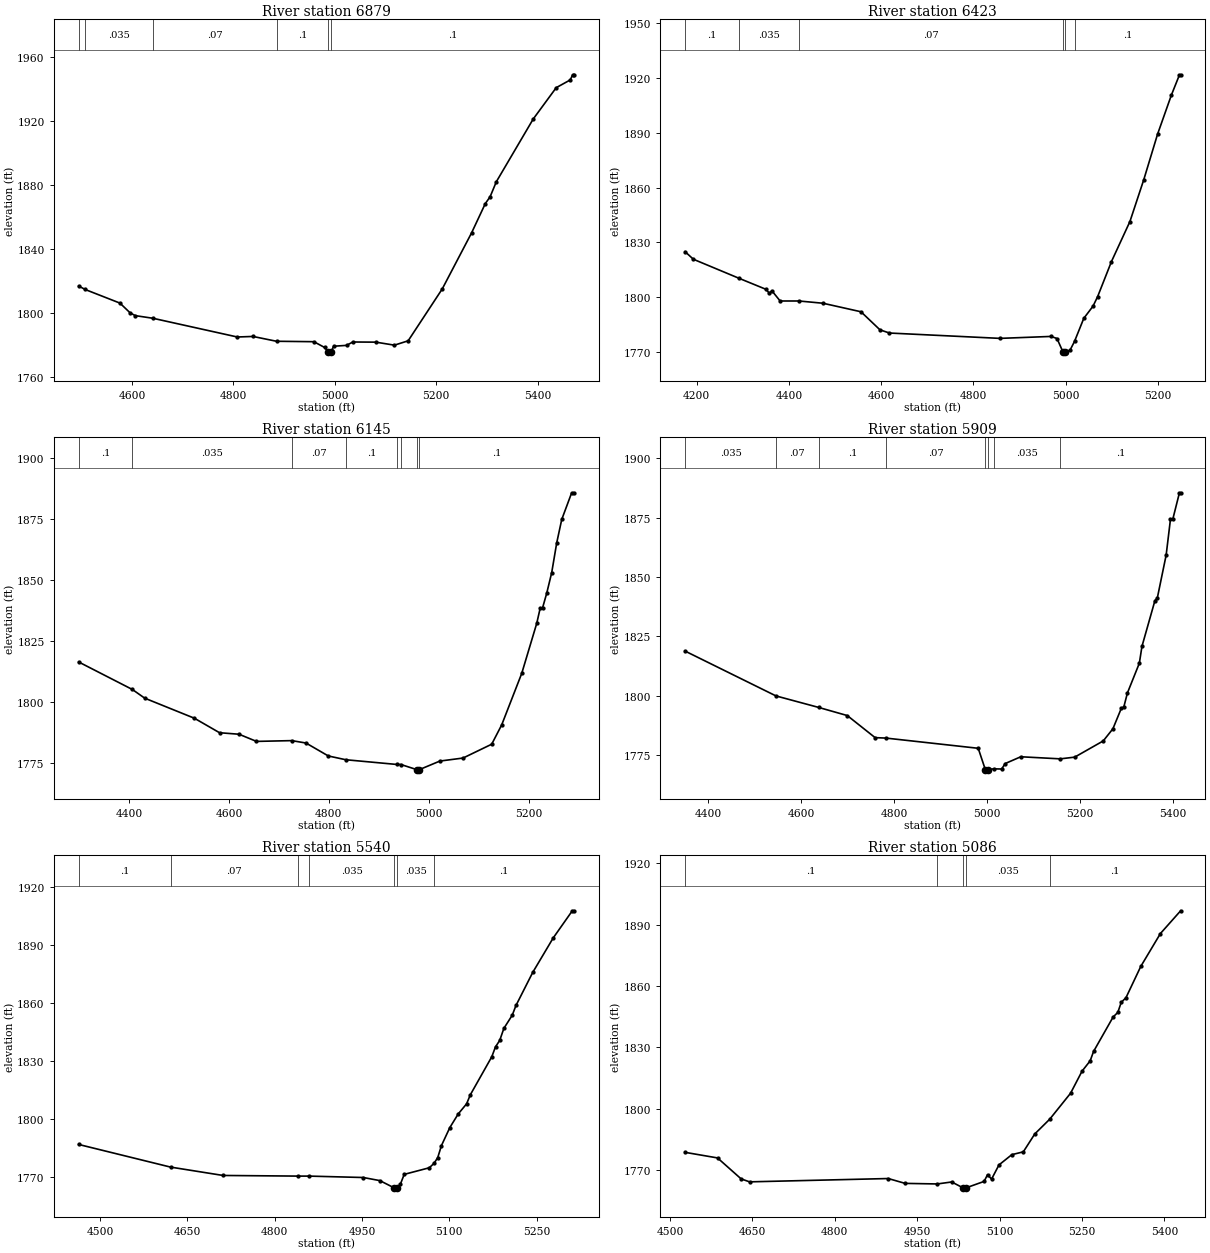
Type RM Length L Ch R = 1,6879,456,456,456
BEGIN DESCRIPTION:
Stream0326 13.0
END DESCRIPTION:
XS GIS Cut Line= 3
      1869492.19     13939625.66      1869425.00     13939125.00
      1869174.97     13938724.96
#Sta/Elev= 30
  4494.9 1816.62  4507.8 1814.41  4576.3 1805.91  4596.5 1799.79  4606.6 1798.08
  4641.2 1796.44  4807.7 1784.73  4838.6 1785.07  4885.0 1782.06  4958.6 1781.79
  4979.9 1778.17  4987.4 1775.33  4987.8 1774.83  4992.6 1775.33  4997.5 1778.96
  5023.0 1779.49  5035.4 1781.61  5080.8 1781.51  5117.4 1779.63  5144.5 1782.34
  5211.7 1814.75  5269.5 1849.75  5296.6 1868.08  5306.1 1872.38  5318.4 1881.77
  5391.0 1920.91  5436.4 1940.52  5464.1 1945.37  5468.8 1948.58  5471.8 1948.58
#Mann=6,-1,0
  4494.9     0.1       0  4507.8   0.035       0  4641.2    0.07       0
  4885.0     0.1       0  4987.4    0.05       0  4992.6     0.1       0
Bank Sta=4987.4,4992.6
Exp/Cntr=0.3,0.1

Type RM Length L Ch R = 1,6423,278,278,278
BEGIN DESCRIPTION:
Stream0326 12.0
END DESCRIPTION:
XS GIS Cut Line= 3
      1869525.01     13939674.97      1869725.00     13938875.00
      1869725.00     13938624.99
#Sta/Elev= 30
  4175.0 1824.85  4193.0 1820.70  4292.2 1810.24  4350.2 1804.24  4357.9 1802.04
  4363.1 1803.46  4381.1 1797.82  4422.0 1797.82  4473.9 1796.59  4556.4 1791.91
  4597.6 1782.00  4618.2 1780.25  4857.9 1777.32  4968.7 1778.39  4981.5 1777.24
  4994.4 1769.89  4994.8 1769.39  4999.6 1769.89  5009.6 1770.77  5019.5 1775.68
  5039.6 1788.32  5059.6 1794.98  5069.6 1800.21  5099.6 1819.46  5139.6 1841.38
  5169.6 1864.29  5199.6 1889.32  5229.6 1910.77  5247.1 1921.86  5249.6 1921.86
#Mann=6,-1,0
  4175.0     0.1       0  4292.2   0.035       0  4422.0    0.07       0
  4994.4    0.05       0  4999.6    0.07       0  5019.5     0.1       0
Bank Sta=4994.4,4999.6
Exp/Cntr=0.3,0.1

Type RM Length L Ch R = 1,6145,236,236,236
BEGIN DESCRIPTION:
Stream0326 11.1
END DESCRIPTION:
XS GIS Cut Line= 4
      1869644.14     13939633.29      1869934.07     13939055.17
      1869982.69     13938942.32      1869993.10     13938720.09
#Sta/Elev= 30
  4299.1 1816.28  4406.7 1804.98  4431.4 1801.42  4530.9 1793.18  4581.2 1787.24
  4620.2 1786.62  4655.2 1783.68  4725.8 1784.00  4754.3 1783.01  4799.0 1777.70
  4834.1 1776.15  4936.7 1774.21  4944.3 1774.20  4976.1 1772.10  4976.5 1771.60
  4981.3 1772.10  5022.3 1775.61  5068.7 1776.85  5126.1 1782.53  5146.1 1790.45
  5186.2 1811.57  5216.2 1832.08  5223.1 1838.29  5228.1 1838.60  5236.2 1844.45
  5246.2 1852.92  5256.3 1865.20  5266.3 1874.74  5286.2 1885.70  5291.2 1885.70
#Mann=8,-1,0
  4299.1     0.1       0  4406.7   0.035       0  4725.8    0.07       0
  4834.1     0.1       0  4936.7   0.035       0  4944.3     0.1       0
  4976.1    0.05       0  4981.3     0.1       0
Bank Sta=4976.1,4981.3
Exp/Cntr=0.3,0.1

Type RM Length L Ch R = 1,5909,369,369,369
BEGIN DESCRIPTION:
Stream0326 11.0
END DESCRIPTION:
XS GIS Cut Line= 3
      1870380.33     13939729.88      1870140.64     13939121.75
      1870025.01     13938725.02
#Sta/Elev= 30
  4350.1 1818.83  4545.8 1799.94  4637.8 1795.09  4699.3 1791.67  4759.2 1782.37
  4782.6 1782.18  4981.2 1777.88  4996.5 1768.88  4997.0 1768.38  5002.1 1768.88
  5014.2 1769.22  5031.6 1769.15  5039.3 1771.45  5072.8 1774.31  5157.8 1773.43
  5188.9 1774.15  5250.4 1780.99  5271.2 1786.11  5289.4 1794.77  5294.6 1795.24
  5302.4 1801.18  5328.1 1813.73  5333.7 1820.80  5361.6 1840.07  5366.8 1841.20
  5385.8 1859.26  5395.1 1874.39  5400.3 1874.54  5414.4 1885.53  5417.0 1885.53
#Mann=8,-1,0
  4350.1   0.035       0  4545.8    0.07       0  4637.8     0.1       0
  4782.6    0.07       0  4996.5    0.05       0  5002.1    0.07       0
  5014.2   0.035       0  5157.8     0.1       0
Bank Sta=4996.5,5002.1
Exp/Cntr=0.3,0.1

Type RM Length L Ch R = 1,5540,454,454,454
BEGIN DESCRIPTION:
Stream0326 10.0
END DESCRIPTION:
XS GIS Cut Line= 3
      1870674.98     13939274.98      1870325.00     13938875.00
      1870125.02     13938625.03
#Sta/Elev= 30
  4463.1 1787.02  4621.1 1775.34  4711.3 1771.03  4839.7 1770.70  4858.9 1770.70
  4952.3 1769.97  4980.8 1768.37  5005.4 1764.63  5005.8 1764.13  5011.0 1764.63
  5016.2 1766.64  5022.6 1771.59  5065.8 1775.00  5073.8 1777.27  5080.2 1780.21
  5086.6 1786.43  5101.0 1795.71  5115.4 1802.74  5129.8 1807.96  5136.3 1812.66
  5173.1 1832.23  5179.5 1837.36  5186.7 1840.63  5193.9 1846.88  5208.3 1853.69
  5214.7 1858.69  5243.5 1875.75  5278.7 1893.53  5311.5 1907.52  5314.7 1907.52
#Mann=7,-1,0
  4463.1     0.1       0  4621.1    0.07       0  4839.7     0.1       0
  4858.9   0.035       0  5005.4   0.035       0  5011.0   0.035       0
  5073.8     0.1       0
Bank Sta=5005.4,5011
Exp/Cntr=0.3,0.1

Type RM Length L Ch R = 1,5086,461,461,461
BEGIN DESCRIPTION:
Stream0326 9.0
END DESCRIPTION:
XS GIS Cut Line= 3
      1870925.00     13939075.01      1870675.00     13938675.00
      1870325.02     13938425.01
#Sta/Elev= 30
  4527.6 1778.69  4586.6 1775.96  4629.6 1765.70  4644.9 1764.26  4897.3 1765.88
  4928.0 1763.51  4986.5 1763.23  5012.8 1764.20  5033.3 1761.34  5033.8 1760.84
  5039.0 1761.34  5071.8 1764.48  5078.0 1767.79  5085.3 1765.59  5098.8 1772.54
  5122.2 1777.56  5143.1 1778.94  5164.0 1787.70  5191.2 1794.92  5229.1 1807.61
  5250.0 1818.41  5264.8 1823.46  5270.9 1828.02  5306.5 1844.88  5315.1 1847.15
  5321.3 1852.06  5329.9 1854.32  5356.9 1869.65  5392.6 1885.72  5429.4 1896.85
#Mann=5,-1,0
  4527.6     0.1       0  4986.5   0.035       0  5033.3   0.035       0
  5039.0   0.035       0  5191.2     0.1       0
Bank Sta=5033.3,5039
Exp/Cntr=0.3,0.1

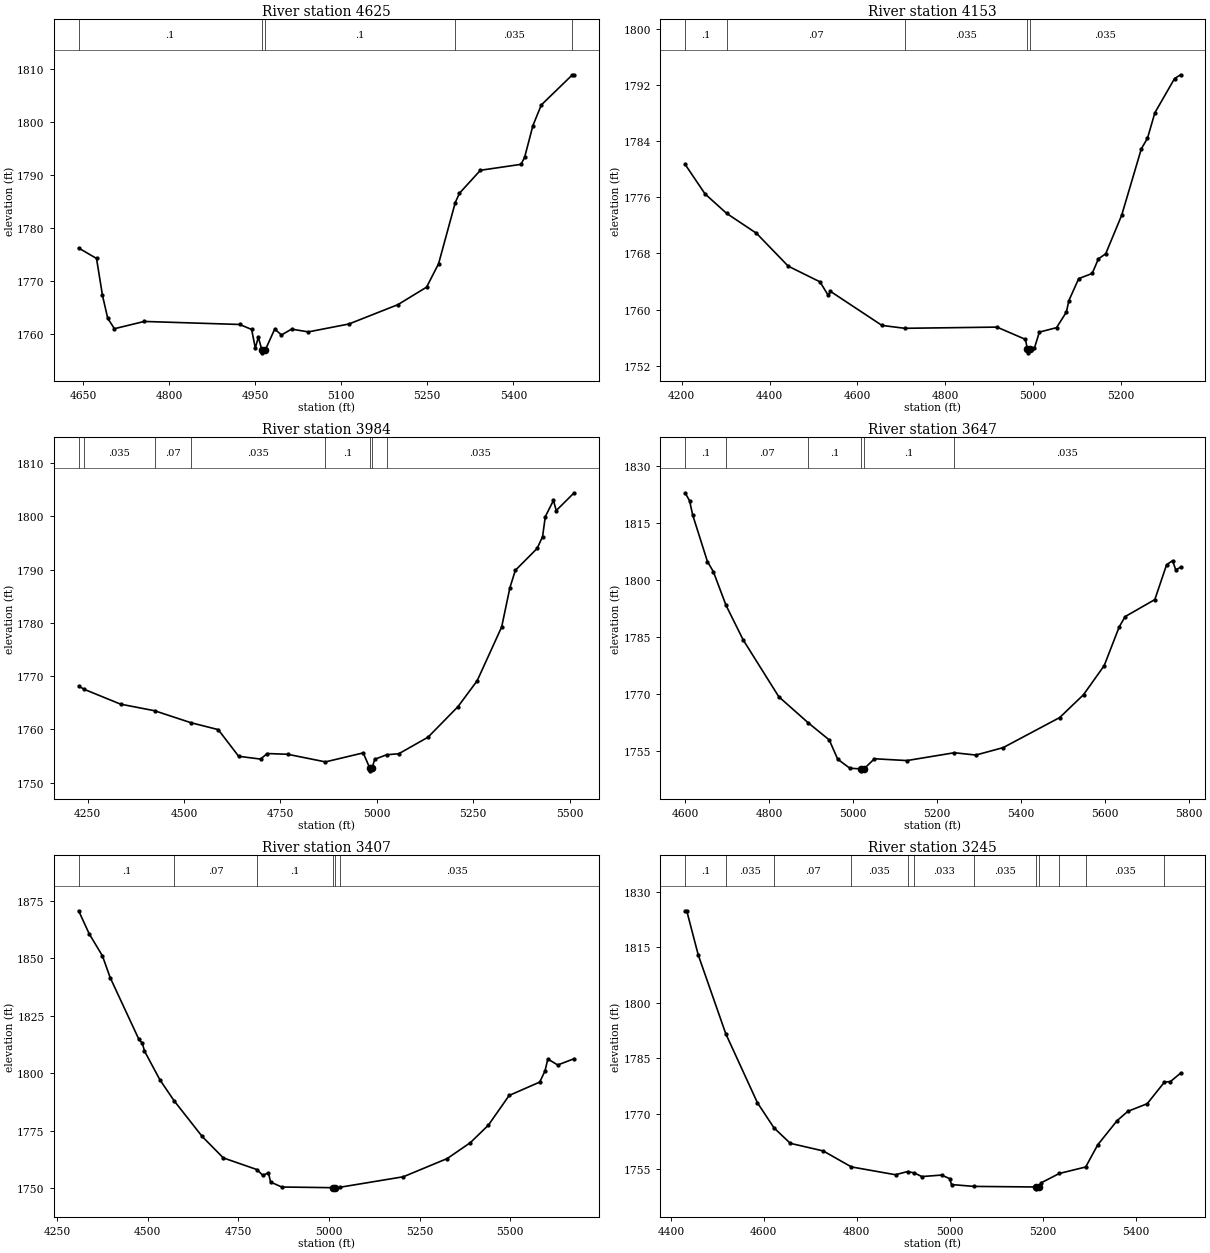
Type RM Length L Ch R = 1,4625,472,472,472
BEGIN DESCRIPTION:
Stream0326 8.0
END DESCRIPTION:
XS GIS Cut Line= 3
      1870975.00     13939025.01      1871075.00     13938675.00
      1870775.01     13938275.01
#Sta/Elev= 30
  4642.1 1776.31  4673.3 1774.34  4683.7 1767.36  4692.8 1763.06  4704.5 1761.09
  4756.5 1762.46  4922.9 1761.89  4943.7 1760.95  4950.2 1757.44  4955.4 1759.49
  4961.7 1757.04  4962.1 1756.54  4967.4 1757.04  4984.0 1761.03  4995.7 1759.91
  5013.4 1761.01  5042.6 1760.49  5113.4 1761.98  5198.8 1765.63  5248.8 1768.93
  5269.7 1773.35  5298.8 1784.89  5306.1 1786.64  5342.6 1790.97  5413.4 1792.09
  5419.7 1793.41  5434.2 1799.41  5448.8 1803.29  5502.8 1808.95  5506.1 1808.98
#Mann=5,-1,0
  4642.1     0.1       0  4961.7    0.05       0  4967.4     0.1       0
  5298.8   0.035       0  5502.8     0.1       0
Bank Sta=4961.7,4967.4
Exp/Cntr=0.3,0.1

Type RM Length L Ch R = 1,4153,169,169,169
BEGIN DESCRIPTION:
Stream0326 7.0
END DESCRIPTION:
XS GIS Cut Line= 3
      1871228.35     13939192.24      1871425.00     13938425.00
      1871275.02     13938125.04
#Sta/Elev= 30
  4207.9 1780.68  4253.2 1776.48  4302.5 1773.70  4370.2 1770.88  4442.5 1766.20
  4514.7 1763.97  4533.5 1762.05  4538.7 1762.61  4655.8 1757.77  4707.7 1757.36
  4917.4 1757.53  4982.1 1755.79  4986.8 1754.37  4987.2 1753.87  4992.5 1754.37
  5002.7 1754.55  5013.9 1756.82  5053.0 1757.45  5075.4 1759.68  5081.0 1761.30
  5103.4 1764.43  5134.1 1765.16  5148.1 1767.23  5164.8 1767.96  5201.2 1773.45
  5245.9 1782.89  5259.9 1784.40  5276.7 1788.02  5321.4 1792.88  5335.3 1793.42
#Mann=5,-1,0
  4207.9     0.1       0  4302.5    0.07       0  4707.7   0.035       0
  4986.8   0.035       0  4992.5   0.035       0
Bank Sta=4986.8,4992.5
Exp/Cntr=0.3,0.1

Type RM Length L Ch R = 1,3984,337,337,337
BEGIN DESCRIPTION:
Stream0326 6.1
END DESCRIPTION:
XS GIS Cut Line= 4
      1871365.68     13939116.92      1871578.35     13938504.93
      1871576.18     13938326.98      1871245.23     13938009.01
#Sta/Elev= 30
  4226.8 1768.13  4241.2 1767.51  4335.7 1764.72  4423.6 1763.49  4517.8 1761.24
  4588.8 1759.94  4641.7 1754.93  4698.4 1754.41  4715.8 1755.45  4768.8 1755.31
  4866.7 1753.88  4964.6 1755.57  4981.8 1752.70  4982.2 1752.20  4987.5 1752.70
  4994.6 1754.37  5025.3 1755.22  5056.9 1755.41  5132.7 1758.52  5210.4 1764.26
  5260.1 1769.12  5323.6 1779.22  5345.0 1786.60  5359.1 1789.86  5415.5 1793.96
  5429.6 1796.17  5436.8 1799.95  5457.9 1802.98  5465.1 1801.08  5511.6 1804.42
#Mann=8,-1,0
  4226.8     0.1       0  4241.2   0.035       0  4423.6    0.07       0
  4517.8   0.035       0  4866.7     0.1       0  4981.8    0.05       0
  4987.5     0.1       0  5025.3   0.035       0
Bank Sta=4981.8,4987.5
Exp/Cntr=0.3,0.1

Type RM Length L Ch R = 1,3647,240,240,240
BEGIN DESCRIPTION:
Stream0326 6.2
END DESCRIPTION:
XS GIS Cut Line= 5
      1872039.58     13938875.67      1871771.39     13938625.70
      1871721.91     13938550.18      1871619.04     13938319.71
      1871269.38     13938003.84
#Sta/Elev= 30
  4600.2 1822.90  4610.9 1820.79  4618.2 1817.09  4653.4 1804.81  4667.6 1802.14
  4697.7 1793.30  4738.4 1784.24  4823.4 1769.26  4893.0 1762.45  4943.6 1757.90
  4963.7 1752.84  4992.6 1750.46  5019.3 1750.27  5019.8 1749.77  5026.3 1750.27
  5051.2 1752.95  5128.5 1752.47  5241.6 1754.53  5292.8 1753.92  5358.0 1755.88
  5492.5 1763.78  5549.3 1769.79  5598.6 1777.44  5634.4 1787.64  5648.6 1790.34
  5719.2 1794.81  5747.3 1803.99  5761.5 1805.04  5769.0 1802.63  5780.7 1803.32
#Mann=6,-1,0
  4600.2     0.1       0  4697.7    0.07       0  4893.0     0.1       0
  5019.3    0.05       0  5026.3     0.1       0  5241.6   0.035       0
Bank Sta=5019.3,5026.3
Exp/Cntr=0.3,0.1

Type RM Length L Ch R = 1,3407,162,162,162
BEGIN DESCRIPTION:
Stream0326 6.0
END DESCRIPTION:
XS GIS Cut Line= 3
      1872125.00     13938974.99      1871769.89     13938397.39
      1871239.49     13937957.35
#Sta/Elev= 30
  4309.1 1870.75  4338.1 1860.77  4374.8 1851.11  4396.1 1841.67  4475.3 1814.80
  4484.9 1813.09  4490.8 1809.70  4533.3 1797.18  4572.6 1788.04  4649.5 1772.60
  4708.2 1763.19  4800.6 1758.13  4817.4 1755.58  4832.8 1756.72  4838.7 1752.67
  4869.5 1750.52  5010.2 1750.22  5010.7 1749.72  5017.2 1750.22  5029.7 1750.40
  5205.1 1754.98  5326.2 1762.92  5390.0 1769.84  5439.5 1777.42  5496.8 1790.35
  5581.4 1796.20  5595.8 1801.04  5603.6 1806.23  5630.9 1803.63  5676.3 1806.37
#Mann=6,-1,0
  4309.1     0.1       0  4572.6    0.07       0  4800.6     0.1       0
  5010.2    0.05       0  5017.2     0.1       0  5029.7   0.035       0
Bank Sta=5010.2,5017.2
Exp/Cntr=0.3,0.1

Type RM Length L Ch R = 1,3245,465,465,465
BEGIN DESCRIPTION:
Stream0326 5.0
END DESCRIPTION:
XS GIS Cut Line= 3
      1872274.98     13938674.98      1871875.00     13938275.00
      1871474.97     13937974.98
#Sta/Elev= 30
  4430.7 1824.92  4434.2 1824.92  4459.0 1812.96  4518.2 1791.66  4586.2 1773.02
  4621.8 1766.23  4656.9 1762.04  4727.7 1759.98  4788.3 1755.66  4883.2 1753.54
  4909.2 1754.41  4923.4 1754.04  4939.8 1753.05  4982.2 1753.45  4999.5 1752.50
  5003.7 1750.89  5051.6 1750.39  5185.6 1750.23  5186.1 1749.73  5192.6 1750.23
  5196.4 1751.35  5235.3 1753.88  5292.2 1755.64  5318.2 1761.65  5359.9 1768.19
  5382.8 1770.68  5424.5 1772.75  5461.6 1778.60  5474.5 1778.74  5496.4 1781.03
#Mann=12,-1,0
  4430.7     0.1       0  4518.2   0.035       0  4621.8    0.07       0
  4788.3   0.035       0  4909.2    0.07       0  4923.4   0.033       0
  5051.6   0.035       0  5185.6   0.033       0  5192.6   0.035       0
  5235.3     0.1       0  5292.2   0.035       0  5461.6     0.1       0
Bank Sta=5185.6,5192.6
Exp/Cntr=0.3,0.1