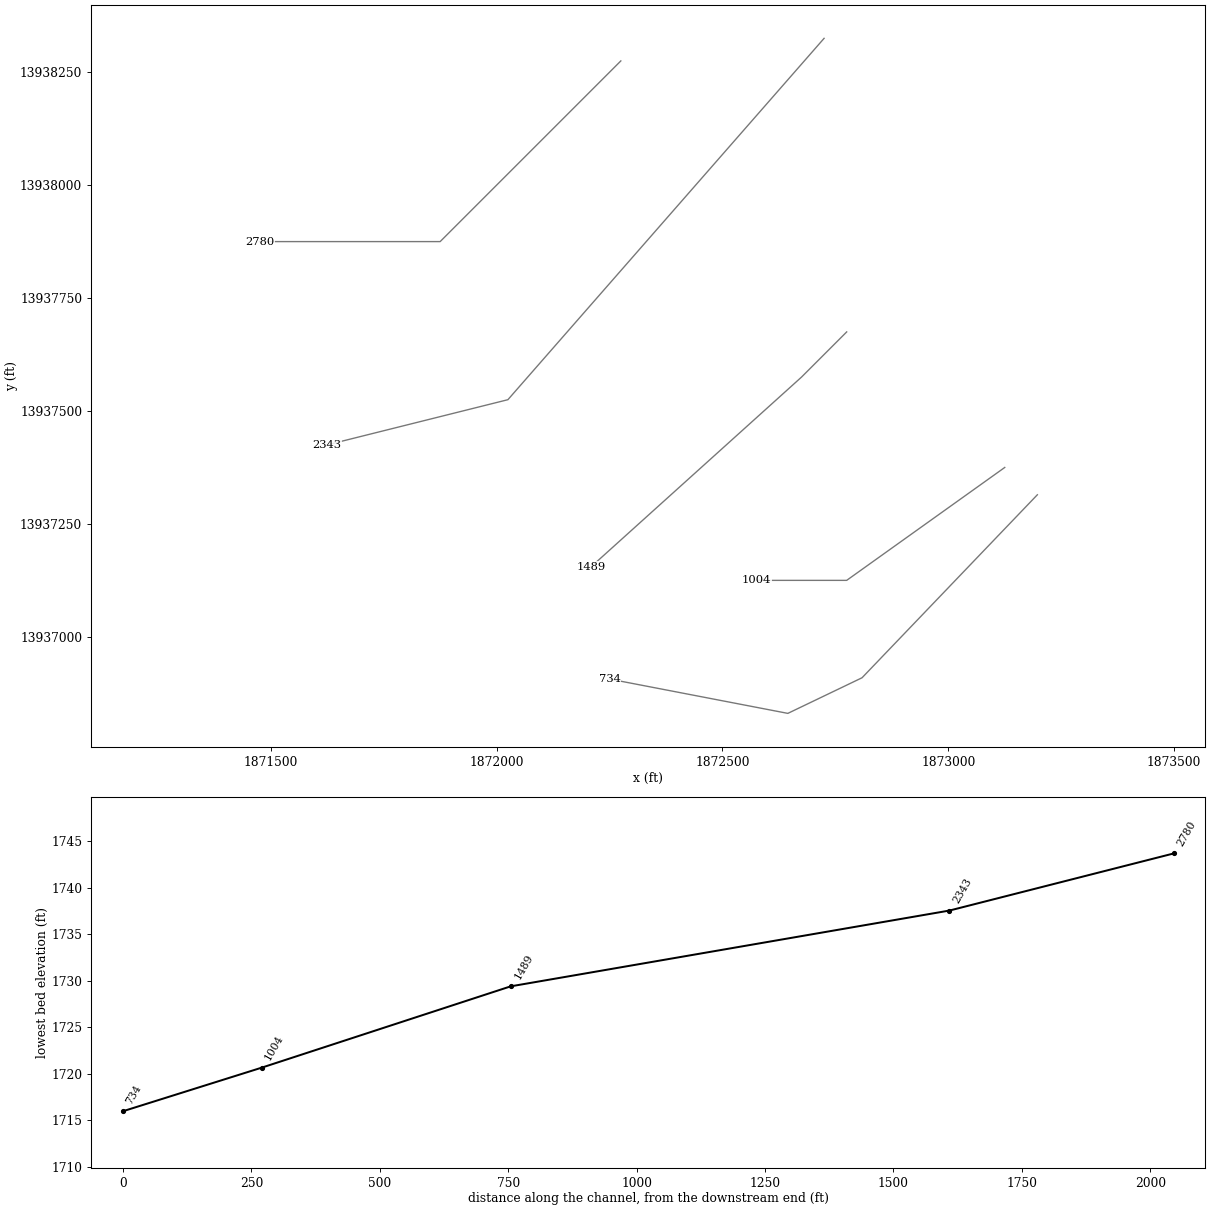
HEC-RAS study Stream0326.prj: Stream0326 Base Level Engineering

--- Stream0326.g01 (geometry) --- (continued)

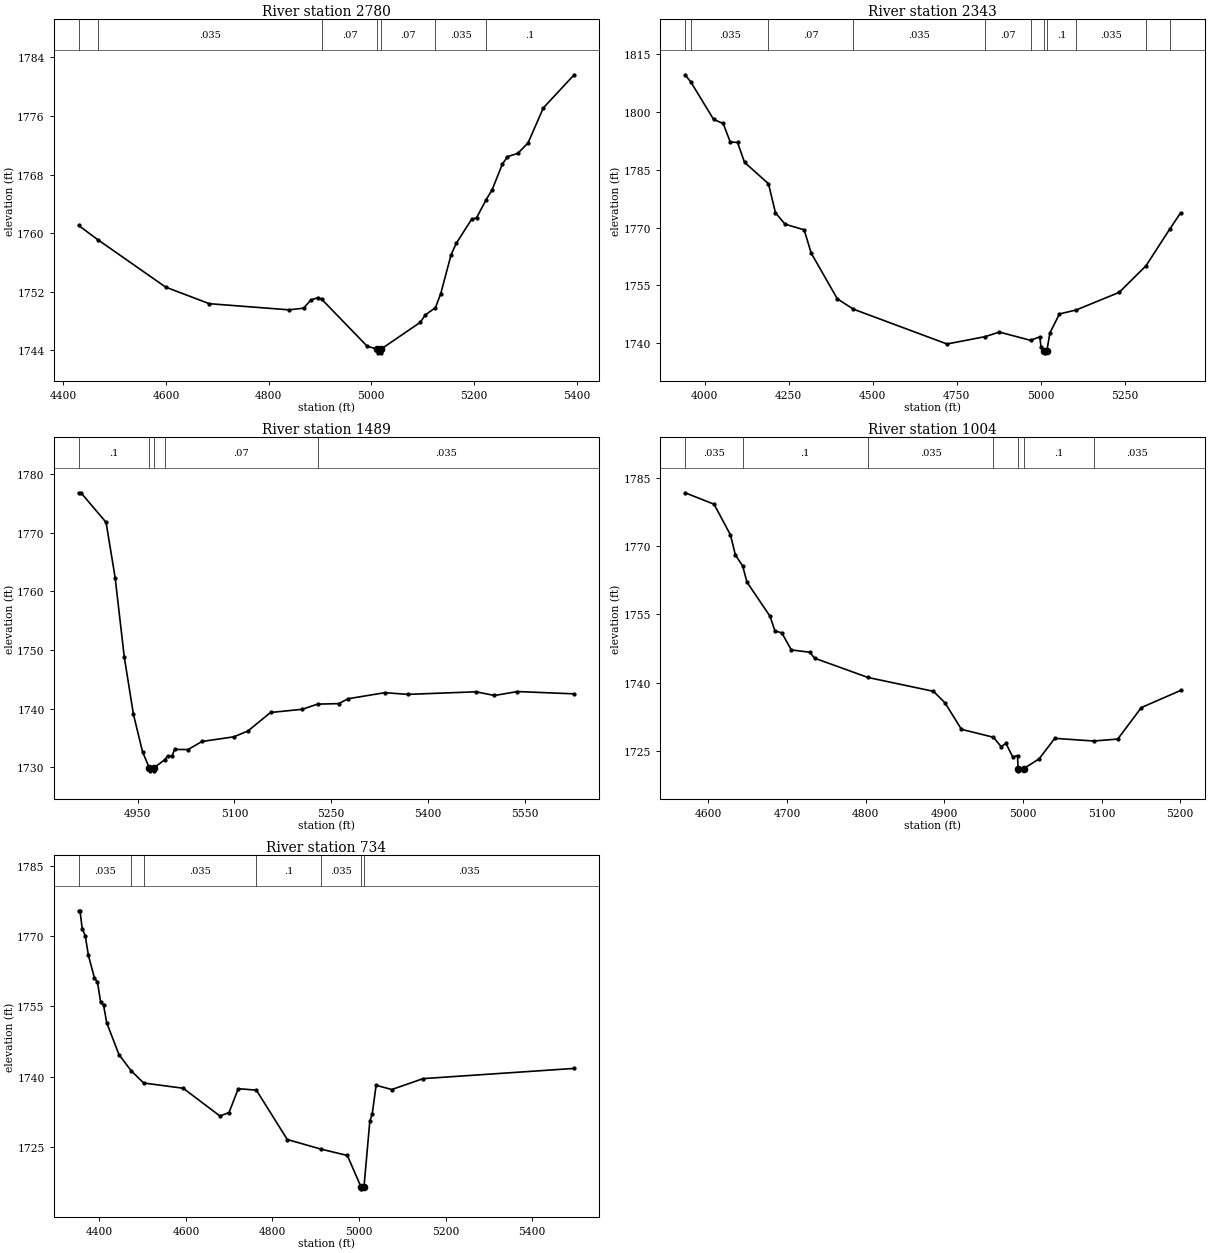
Type RM Length L Ch R = 1,2780,437,437,437
BEGIN DESCRIPTION:
Stream0326 4.0
END DESCRIPTION:
XS GIS Cut Line= 3
      1872275.00     13938275.00      1871875.00     13937875.00
      1871474.99     13937875.00
#Sta/Elev= 30
  4429.6 1761.07  4466.5 1759.15  4599.3 1752.65  4684.2 1750.39  4839.7 1749.55
  4868.0 1749.78  4882.2 1750.89  4896.3 1751.23  4903.7 1750.97  4991.8 1744.59
  5011.7 1744.18  5012.2 1743.68  5018.3 1743.68  5018.8 1744.18  5095.3 1747.84
  5105.3 1748.86  5125.0 1749.85  5135.3 1751.77  5155.3 1757.04  5165.3 1758.61
  5195.3 1761.89  5205.3 1762.14  5223.6 1764.57  5235.3 1765.92  5255.3 1769.43
  5265.3 1770.46  5285.3 1770.91  5305.3 1772.32  5335.3 1777.13  5395.3 1781.64
#Mann=7,-1,0
  4429.6    0.07       0  4466.5   0.035       0  4903.7    0.07       0
  5011.7    0.05       0  5018.8    0.07       0  5125.0   0.035       0
  5223.6     0.1       0
Bank Sta=5011.7,5018.8
Exp/Cntr=0.3,0.1

Type RM Length L Ch R = 1,2343,854,854,854
BEGIN DESCRIPTION:
Stream0326 3.0
END DESCRIPTION:
XS GIS Cut Line= 3
      1872725.00     13938325.00      1872025.00     13937525.00
      1871625.03     13937425.01
#Sta/Elev= 30
  3941.6 1809.57  3959.1 1807.64  4026.6 1797.99  4055.0 1796.96  4075.9 1792.17
  4097.7 1792.03  4118.6 1786.88  4189.8 1781.35  4210.7 1773.81  4239.2 1770.87
  4296.1 1769.40  4317.0 1763.38  4394.8 1751.53  4442.5 1748.86  4721.3 1739.83
  4835.6 1741.75  4877.0 1742.92  4970.1 1740.78  4997.5 1741.68  5001.3 1739.07
  5011.4 1738.04  5011.9 1737.54  5018.5 1738.04  5027.8 1742.73  5056.2 1747.62
  5106.3 1748.65  5234.0 1753.21  5313.7 1760.08  5384.2 1769.56  5416.9 1773.82
#Mann=11,-1,0
  3941.6     0.1       0  3959.1   0.035       0  4189.8    0.07       0
  4442.5   0.035       0  4835.6    0.07       0  4970.1     0.1       0
  5011.4    0.05       0  5018.5     0.1       0  5106.3   0.035       0
  5313.7     0.1       0  5384.2    0.07       0
Bank Sta=5011.4,5018.5
Exp/Cntr=0.3,0.1

Type RM Length L Ch R = 1,1489,485,485,485
BEGIN DESCRIPTION:
Stream0326 2.0
END DESCRIPTION:
XS GIS Cut Line= 3
      1872775.03     13937675.03      1872675.00     13937575.00
      1872209.86     13937155.69
#Sta/Elev= 30
  4858.6 1776.82  4862.2 1776.82  4901.1 1771.78  4915.2 1762.32  4929.3 1748.82
  4943.5 1739.04  4957.6 1732.65  4968.1 1729.90  4968.6 1729.40  4974.9 1729.40
  4975.4 1729.90  4992.1 1731.32  4996.5 1731.91  5003.4 1731.91  5007.2 1733.05
  5028.1 1733.03  5049.8 1734.41  5099.1 1735.20  5120.8 1736.19  5155.9 1739.35
  5205.2 1739.90  5228.8 1740.78  5261.4 1740.86  5276.2 1741.70  5333.0 1742.73
  5368.1 1742.44  5474.3 1742.88  5502.7 1742.25  5538.5 1742.92  5626.3 1742.53
#Mann=5,-1,0
  4858.6     0.1       0  4968.1    0.05       0  4975.4     0.1       0
  4992.1    0.07       0  5228.8   0.035       0
Bank Sta=4968.1,4975.4
Exp/Cntr=0.3,0.1

Type RM Length L Ch R = 1,1004,270,270,270
BEGIN DESCRIPTION:
Stream0326 1.0
END DESCRIPTION:
XS GIS Cut Line= 3
      1873124.97     13937374.98      1872775.00     13937125.00
      1872574.98     13937125.00
#Sta/Elev= 30
  4570.4 1781.69  4607.2 1779.18  4628.1 1772.44  4634.3 1768.06  4643.7 1765.59
  4649.0 1762.10  4678.5 1754.56  4684.6 1751.36  4693.3 1750.96  4705.5 1747.20
  4728.9 1746.69  4735.0 1745.39  4802.8 1741.16  4886.2 1738.11  4900.9 1735.58
  4921.8 1729.77  4962.5 1728.03  4972.2 1725.98  4978.4 1726.67  4987.0 1723.72
  4993.1 1724.01  4993.8 1721.16  4994.3 1720.66  5001.1 1721.16  5020.5 1723.29
  5040.5 1727.79  5089.9 1727.21  5120.5 1727.63  5150.5 1734.54  5200.5 1738.31
#Mann=7,-1,0
  4570.4   0.035       0  4643.7     0.1       0  4802.8   0.035       0
  4962.5     0.1       0  4993.8    0.05       0  5001.1     0.1       0
  5089.9   0.035       0
Bank Sta=4993.8,5001.1
Exp/Cntr=0.3,0.1

Type RM Length L Ch R = 1,734,0,0,0
BEGIN DESCRIPTION:
Stream0326 0.0
END DESCRIPTION:
XS GIS Cut Line= 4
      1873197.16     13937314.51      1872809.06     13936909.39
      1872644.73     13936830.53      1872249.98     13936906.55
#Sta/Elev= 30
  4352.0 1775.44  4355.1 1775.44  4360.3 1771.62  4367.2 1770.14  4374.5 1765.96
  4388.6 1761.03  4395.5 1760.22  4402.8 1755.94  4409.7 1755.19  4416.9 1751.51
  4445.2 1744.68  4473.4 1741.23  4502.3 1738.61  4593.7 1737.49  4678.6 1731.55
  4699.6 1732.30  4721.0 1737.40  4762.8 1737.08  4834.2 1726.53  4912.2 1724.47
  4973.0 1723.12  5004.2 1716.48  5004.7 1715.98  5011.6 1716.48  5025.0 1730.44
  5030.6 1732.01  5039.5 1738.12  5075.9 1737.22  5148.2 1739.55  5497.3 1741.73
#Mann=7,-1,0
  4352.0   0.035       0  4473.4     0.1       0  4502.3   0.035       0
  4762.8     0.1       0  4912.2   0.035       0  5004.2   0.035       0
  5011.6   0.035       0
Bank Sta=5004.2,5011.6
Exp/Cntr=0.3,0.1

Chan Stop Cuts=-1