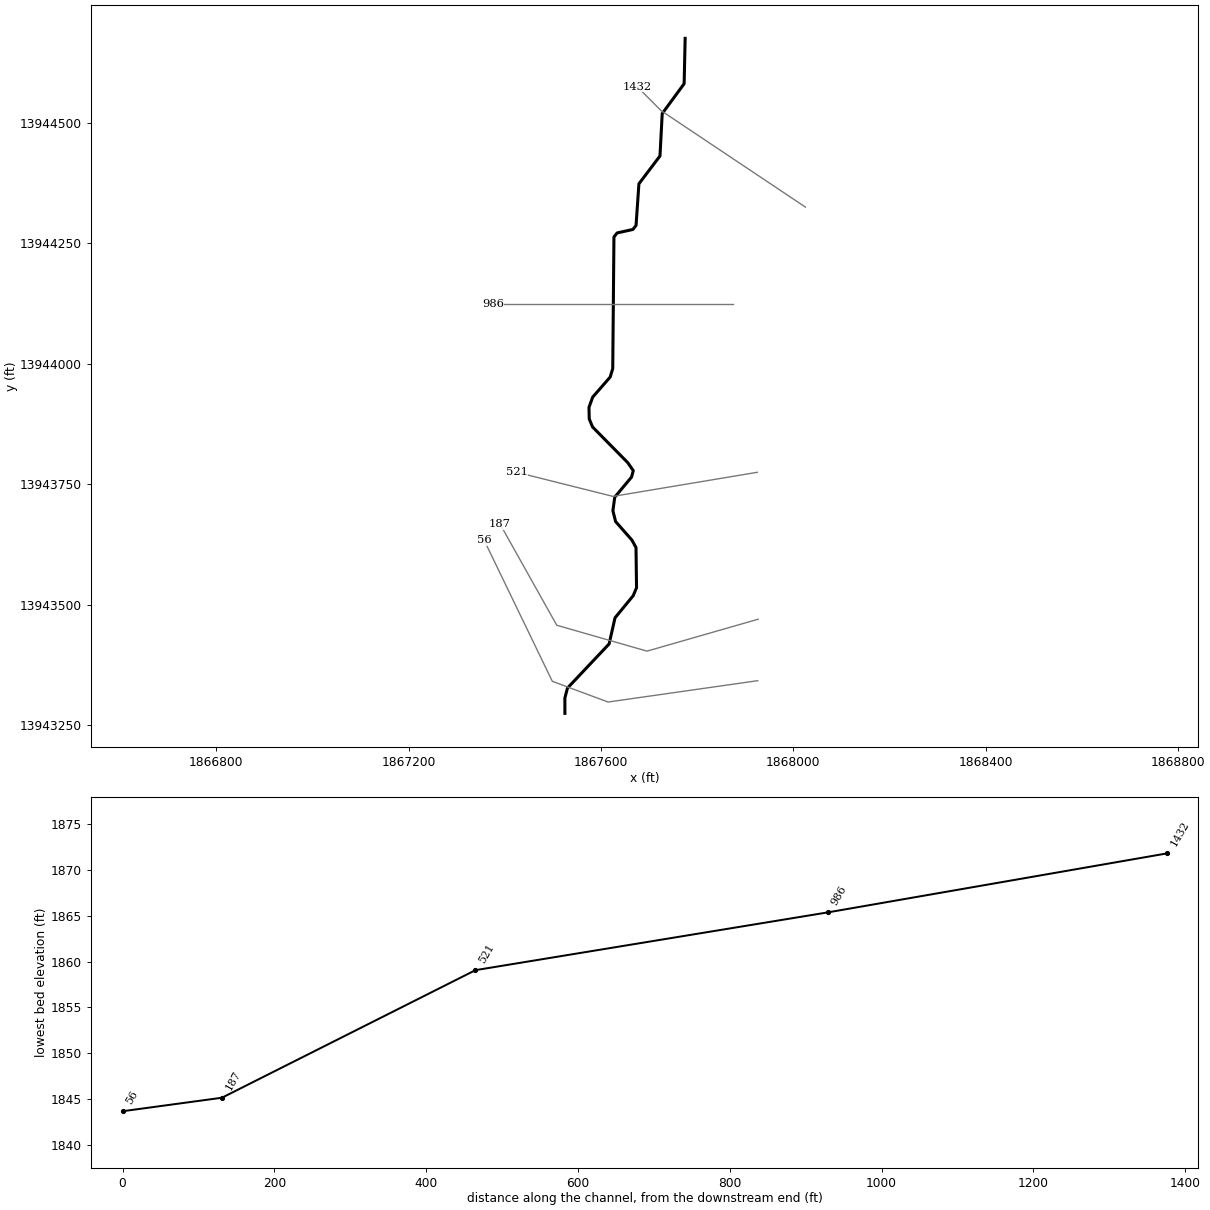
--- Stream0327.prj (project) ---

Proj Title=Stream0327 Base Level Engineering
Current Plan=p01
Default Exp/Contr=0.3,0.1
English Units
Geom File=g01
Flow File=f01
Plan File=p01
BEGIN DESCRIPTION:
Stream0327
END DESCRIPTION:

--- Stream0327.p01 (plan) ---

Plan Title=Multiple Run
Short Identifier=Multiple
Geom File=g01
Flow File=f01
Subcritical Flow
K Sum by GR= 0
Std Step Tol= 0.01
Critical Tol= 0.01
Num of Std Step Trials= 20
Max Error Tol= 0.3
Flow Tol Ratio= 0.001
Split Flow NTrial= 30
Split Flow Tol= 0.02
Split Flow Ratio= 0.02
Log Output Level= 0
Friction Slope Method= 1
Unsteady Friction Slope Method= 2
Unsteady Bridges Friction Slope Method= 1
Parabolic Critical Depth
Global Vel Dist=  1 , 1 , 1
Global Log Level= 0
CheckData=True
Encroach Param= -1, 0, 0, 0
BEGIN DESCRIPTION:
Multiple Run
END DESCRIPTION:

--- Stream0327.f01 (steady flow) ---

Flow Title=Multiple
Number of Profiles=7
Profile Names=10-year,25-year,50-year,1pct_min,100-year,1pct_plu,500-year
River Rch & RM= Stream0327,Reach-1,1432
     802    1355    1876    1260    2514    5017    4452
Boundary for River Rch & Prof#=Stream0327,Reach-1,1
Up Type=0
Dn Type=3
Dn Slope=0.005
Boundary for River Rch & Prof#=Stream0327,Reach-1,2
Up Type=0
Dn Type=3
Dn Slope=0.005
Boundary for River Rch & Prof#=Stream0327,Reach-1,3
Up Type=0
Dn Type=3
Dn Slope=0.005
Boundary for River Rch & Prof#=Stream0327,Reach-1,4
Up Type=0
Dn Type=3
Dn Slope=0.005
Boundary for River Rch & Prof#=Stream0327,Reach-1,5
Up Type=0
Dn Type=3
Dn Slope=0.005
Boundary for River Rch & Prof#=Stream0327,Reach-1,6
Up Type=0
Dn Type=3
Dn Slope=0.005
Boundary for River Rch & Prof#=Stream0327,Reach-1,7
Up Type=0
Dn Type=3
Dn Slope=0.005

--- Stream0327.g01 (geometry) ---

Geom Title=Existing Conditions

River Reach=Stream0327,Reach-1
Reach XY= 30
      1867775.00     13944675.00      1867772.90     13944580.87
      1867727.33     13944519.03      1867722.65     13944430.97
      1867678.88     13944373.33      1867672.92     13944287.02
      1867666.35     13944278.61      1867633.57     13944271.42
      1867626.96     13944263.03      1867624.46     13943990.21
      1867619.21     13943972.65      1867582.79     13943930.91
      1867575.04     13943909.58      1867575.61     13943885.62
      1867582.52     13943868.94      1867655.65     13943795.01
      1867667.16     13943778.40      1867663.61     13943765.13
      1867628.62     13943723.37      1867624.79     13943695.21
      1867630.41     13943672.83      1867664.13     13943634.65
      1867672.81     13943619.03      1867673.92     13943535.54
      1867666.96     13943518.95      1867629.22     13943473.25
      1867616.86     13943418.94      1867530.33     13943327.51
      1867524.93     13943306.88      1867525.00     13943275.00

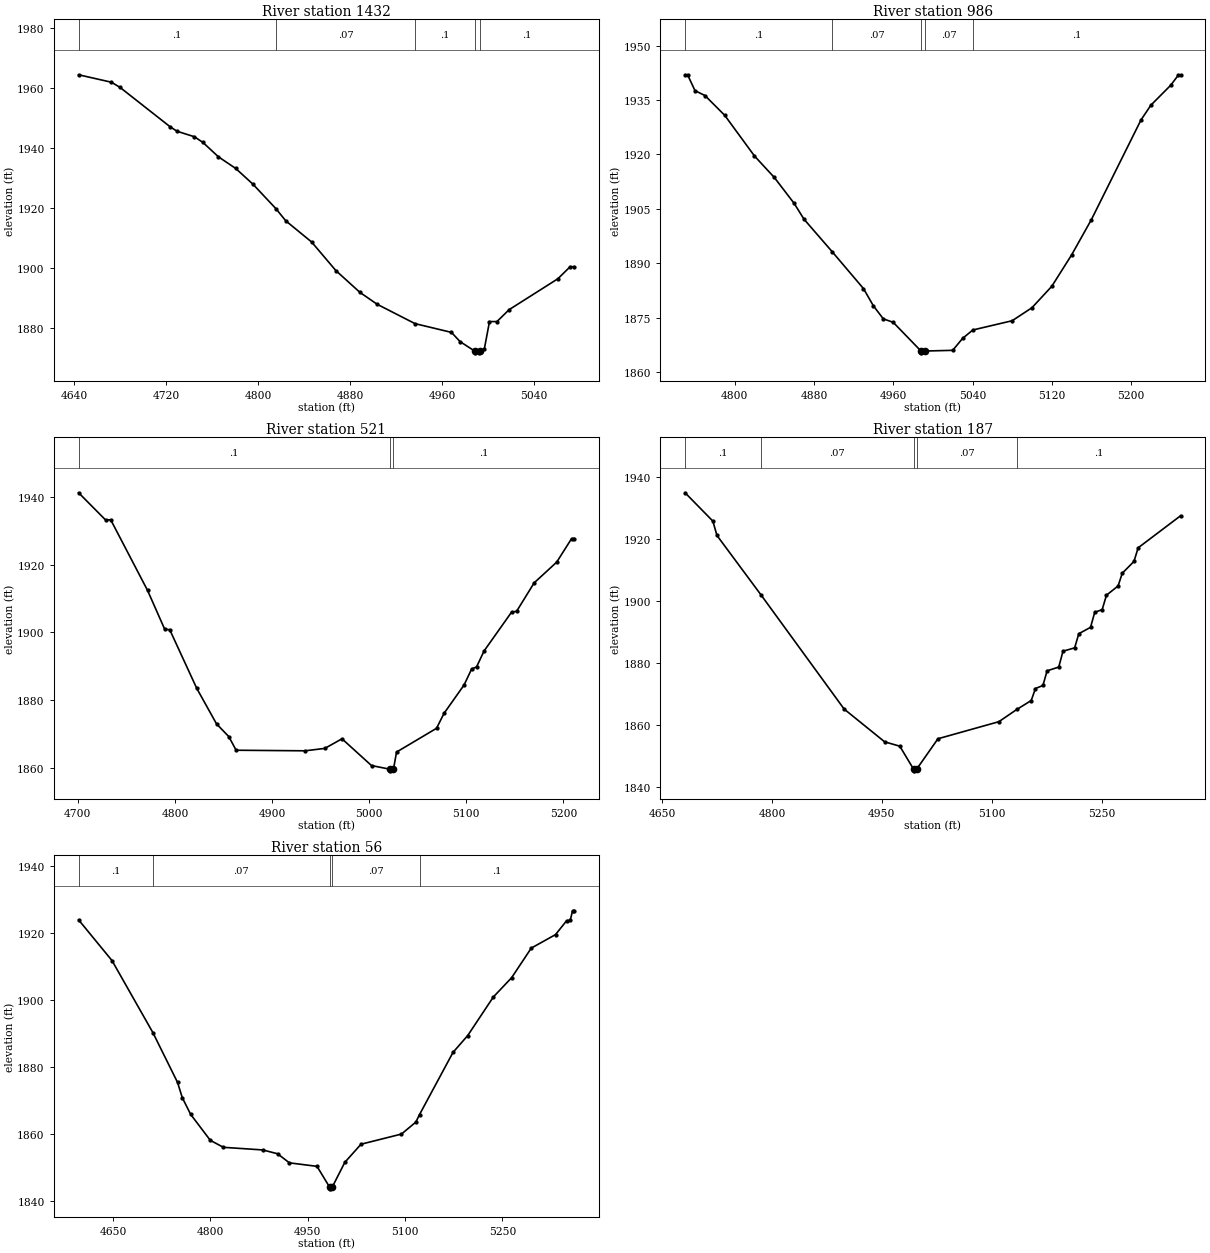
Type RM Length L Ch R = 1,1432,446,446,446
BEGIN DESCRIPTION:
Stream0327 3.0
END DESCRIPTION:
XS GIS Cut Line= 3
      1868025.02     13944324.99      1867725.00     13944525.00
      1867674.99     13944575.01
#Sta/Elev= 30
  4643.7 1964.50  4672.3 1962.01  4679.8 1960.27  4723.3 1947.17  4729.4 1945.66
  4744.4 1943.84  4751.9 1941.93  4765.4 1937.13  4780.4 1933.27  4795.5 1927.98
  4815.4 1919.85  4824.0 1915.79  4846.5 1908.73  4867.6 1899.20  4888.6 1891.91
  4903.6 1887.95  4936.5 1881.51  4968.2 1878.59  4975.7 1875.51  4988.8 1872.27
  4989.0 1871.77  4992.5 1871.77  4992.8 1872.27  4996.8 1873.05  5001.3 1882.20
  5007.8 1882.20  5018.4 1886.17  5060.8 1896.47  5071.5 1900.49  5075.0 1900.49
#Mann=5,-1,0
  4643.7     0.1       0  4815.4    0.07       0  4936.5     0.1       0
  4988.8    0.05       0  4992.8     0.1       0
Bank Sta=4988.8,4992.8
Exp/Cntr=0.3,0.1

Type RM Length L Ch R = 1,986,465,465,465
BEGIN DESCRIPTION:
Stream0327 2.0
END DESCRIPTION:
XS GIS Cut Line= 3
      1867874.99     13944125.00      1867625.00     13944125.00
      1867374.99     13944125.00
#Sta/Elev= 30
  4750.0 1941.95  4752.5 1941.95  4760.0 1937.57  4770.0 1936.24  4790.0 1930.78
  4820.0 1919.58  4840.0 1913.67  4860.0 1906.54  4870.0 1902.16  4898.3 1893.25
  4930.0 1883.05  4940.0 1878.30  4950.0 1874.72  4960.0 1873.76  4988.0 1865.86
  4988.2 1865.36  4992.0 1865.86  5020.0 1866.05  5030.0 1869.34  5040.3 1871.65
  5080.0 1874.20  5100.0 1877.79  5120.0 1883.69  5140.0 1892.34  5160.0 1902.08
  5210.0 1929.51  5220.0 1933.58  5240.0 1939.07  5247.5 1941.79  5250.0 1941.79
#Mann=5,-1,0
  4750.0     0.1       0  4898.3    0.07       0  4988.0    0.05       0
  4992.0    0.07       0  5040.3     0.1       0
Bank Sta=4988,4992
Exp/Cntr=0.3,0.1

Type RM Length L Ch R = 1,521,334,334,334
BEGIN DESCRIPTION:
Stream0327 1.0
END DESCRIPTION:
XS GIS Cut Line= 3
      1867925.02     13943775.00      1867625.00     13943725.00
      1867425.01     13943775.00
#Sta/Elev= 30
  4700.8 1941.24  4728.7 1933.16  4733.8 1933.28  4771.8 1912.37  4789.5 1900.86
  4794.6 1900.78  4822.5 1883.40  4842.8 1872.94  4855.4 1869.19  4863.0 1865.15
  4934.0 1864.98  4954.3 1865.69  4972.0 1868.53  5002.4 1860.62  5021.0 1859.56
  5021.2 1859.06  5025.0 1859.56  5028.2 1864.61  5069.4 1871.64  5077.1 1876.06
  5097.7 1884.42  5105.5 1889.15  5110.6 1889.78  5118.3 1894.48  5146.7 1905.99
  5151.8 1906.20  5169.9 1914.62  5193.1 1920.74  5208.5 1927.72  5211.1 1927.72
#Mann=3,-1,0
  4700.8     0.1       0  5021.0    0.05       0  5025.0     0.1       0
Bank Sta=5021,5025
Exp/Cntr=0.3,0.1

Type RM Length L Ch R = 1,187,131,131,131
BEGIN DESCRIPTION:
Stream0327 0.0
END DESCRIPTION:
XS GIS Cut Line= 4
      1867926.84     13943470.29      1867695.67     13943404.09
      1867508.13     13943457.76      1867390.04     13943667.81
#Sta/Elev= 30
  4681.4 1934.77  4719.3 1925.64  4724.9 1921.01  4785.1 1901.84  4898.5 1865.08
  4953.8 1854.52  4974.5 1853.11  4993.4 1845.67  4993.6 1845.17  4997.4 1845.67
  5026.6 1855.51  5109.8 1861.01  5134.2 1864.95  5153.9 1867.82  5159.7 1871.70
  5169.9 1872.67  5175.6 1877.40  5191.5 1878.61  5197.3 1883.72  5213.2 1884.80
  5218.9 1889.36  5234.9 1891.41  5240.6 1896.24  5250.8 1897.12  5256.6 1901.76
  5272.5 1904.74  5278.2 1908.84  5294.2 1912.66  5299.9 1917.04  5357.9 1927.38
#Mann=5,-1,0
  4681.4     0.1       0  4785.1    0.07       0  4993.4    0.05       0
  4997.4    0.07       0  5134.2     0.1       0
Bank Sta=4993.4,4997.4
Exp/Cntr=0.3,0.1

Type RM Length L Ch R = 1,56,0,0,0
BEGIN DESCRIPTION:
Stream0327 0.1
END DESCRIPTION:
XS GIS Cut Line= 4
      1867925.90     13943342.82      1867614.71     13943298.54
      1867498.82     13943341.51      1867356.88     13943634.52
#Sta/Elev= 30
  4597.0 1923.97  4648.4 1911.83  4711.4 1890.33  4749.4 1875.46  4756.7 1870.91
  4769.6 1865.93  4799.9 1858.17  4820.1 1856.09  4880.7 1855.31  4903.5 1854.17
  4921.7 1851.46  4964.3 1850.41  4983.7 1844.20  4983.9 1843.70  4987.7 1844.20
  5007.1 1851.60  5032.1 1857.02  5094.4 1860.05  5116.6 1863.63  5122.2 1865.85
  5173.8 1884.42  5196.4 1889.43  5236.0 1900.97  5264.1 1906.71  5294.4 1915.55
  5331.8 1919.58  5348.9 1923.74  5354.4 1923.79  5358.0 1926.69  5360.5 1926.69
#Mann=5,-1,0
  4597.0     0.1       0  4711.4    0.07       0  4983.7    0.05       0
  4987.7    0.07       0  5122.2     0.1       0
Bank Sta=4983.7,4987.7
Exp/Cntr=0.3,0.1

Chan Stop Cuts=-1