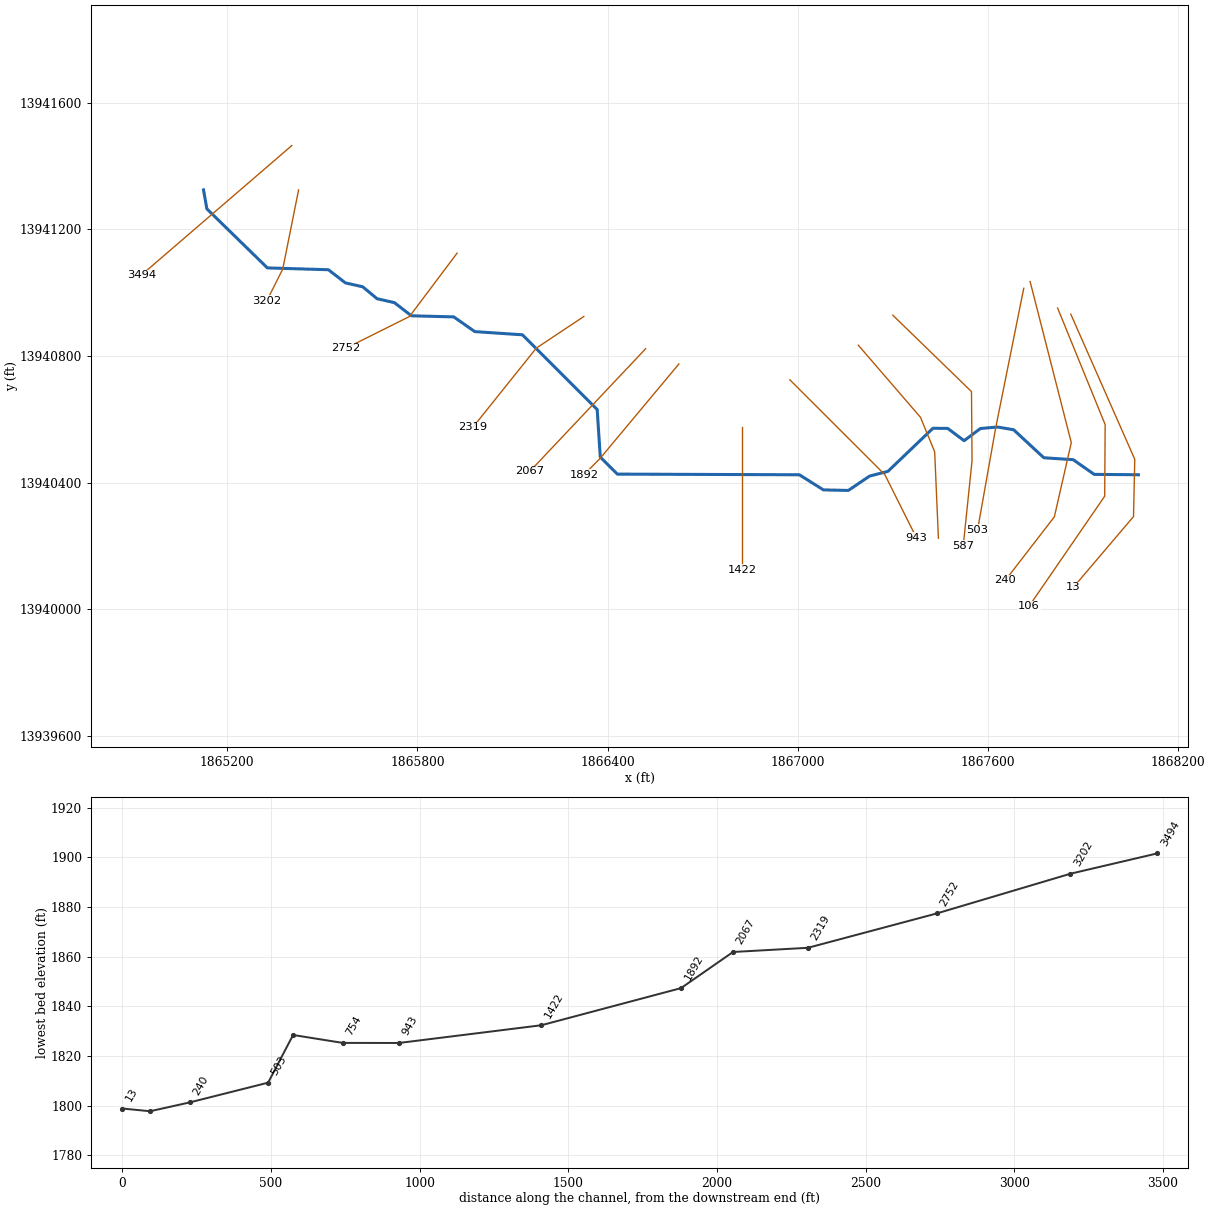
--- Stream0328.prj (project) ---

Proj Title=Stream0328 Base Level Engineering
Current Plan=p01
Default Exp/Contr=0.3,0.1
English Units
Geom File=g01
Flow File=f01
Plan File=p01
Y Axis Title=Elevation
X Axis Title(PF)=Main Channel Distance
X Axis Title(XS)=Station
BEGIN DESCRIPTION:
Stream0328
END DESCRIPTION:
DSS Export Rating Curves= 0
DSS Export Rating Curve Sorted= 0
DSS Export Volume Flow Curves= 0
DXF OffsetX= 0
DXF OffsetY= 0
DXF ScaleX= 1
DXF ScaleY= 10

--- Stream0328.p01 (plan) ---

Plan Title=Multiple Run
Short Identifier=Multiple
Geom File=g01
Flow File=f01
Subcritical Flow
K Sum by GR= 0
Std Step Tol= 0.01
Critical Tol= 0.01
Num of Std Step Trials= 20
Max Error Tol= 0.3
Flow Tol Ratio= 0.001
Split Flow NTrial= 30
Split Flow Tol= 0.02
Split Flow Ratio= 0.02
Log Output Level= 0
Friction Slope Method= 1
Unsteady Friction Slope Method= 2
Unsteady Bridges Friction Slope Method= 1
Parabolic Critical Depth
Global Vel Dist=  1 , 1 , 1
Global Log Level= 0
CheckData=True
Encroach Param= -1, 0, 0, 0
BEGIN DESCRIPTION:
Multiple Run
END DESCRIPTION:

--- Stream0328.f01 (steady flow) ---

Flow Title=Multiple
Program Version=4.10
Number of Profiles= 7
Profile Names=10-year,25-year,50-year,1pct_min,100-year,1pct_plu,500-year
River Rch & RM=Stream0328,Reach-1         ,3494
     747    1254    1731    1159    2312    4613    4064
Boundary for River Rch & Prof#=Stream0328,Reach-1         , 1
Up Type= 0
Dn Type= 3
Dn Slope=0.005
Boundary for River Rch & Prof#=Stream0328,Reach-1         , 2
Up Type= 0
Dn Type= 3
Dn Slope=0.005
Boundary for River Rch & Prof#=Stream0328,Reach-1         , 3
Up Type= 0
Dn Type= 3
Dn Slope=0.005
Boundary for River Rch & Prof#=Stream0328,Reach-1         , 4
Up Type= 0
Dn Type= 3
Dn Slope=0.005
Boundary for River Rch & Prof#=Stream0328,Reach-1         , 5
Up Type= 0
Dn Type= 3
Dn Slope=0.005
Boundary for River Rch & Prof#=Stream0328,Reach-1         , 6
Up Type= 0
Dn Type= 3
Dn Slope=0.005
Boundary for River Rch & Prof#=Stream0328,Reach-1         , 7
Up Type= 0
Dn Type= 3
Dn Slope=0.005
DSS Import GetInterval= 0
DSS Import GetPeak= 0
DSS Import FillOption= 0

--- Stream0328.g01 (geometry) ---

Geom Title=Existing Conditions
Program Version=4.10

River Reach=Stream0328      ,Reach-1
Reach XY= 30
        1865125.       13941325.      1865135.51     13941265.21
      1865326.46     13941078.54      1865519.07     13941072.76
      1865572.82     13941031.12       1865627.2     13941018.92
       1865672.8     13940981.08      1865727.18     13940968.88
      1865780.93     13940927.25      1865914.49     13940923.77
      1865980.94     13940877.27      1866131.19     13940867.18
      1866367.18     13940631.19      1866376.98     13940480.65
      1866430.65     13940426.97      1867004.97     13940424.93
      1867080.98     13940377.17      1867159.73     13940375.37
      1867226.75     13940420.78      1867284.68     13940435.76
      1867426.65     13940571.84      1867473.35     13940571.43
      1867524.99      13940532.6       1867576.5     13940571.07
      1867630.04     13940575.82      1867681.16     13940567.22
       1867776.5     13940478.62      1867869.02     13940472.64
      1867935.48     13940426.17        1868075.       13940425.

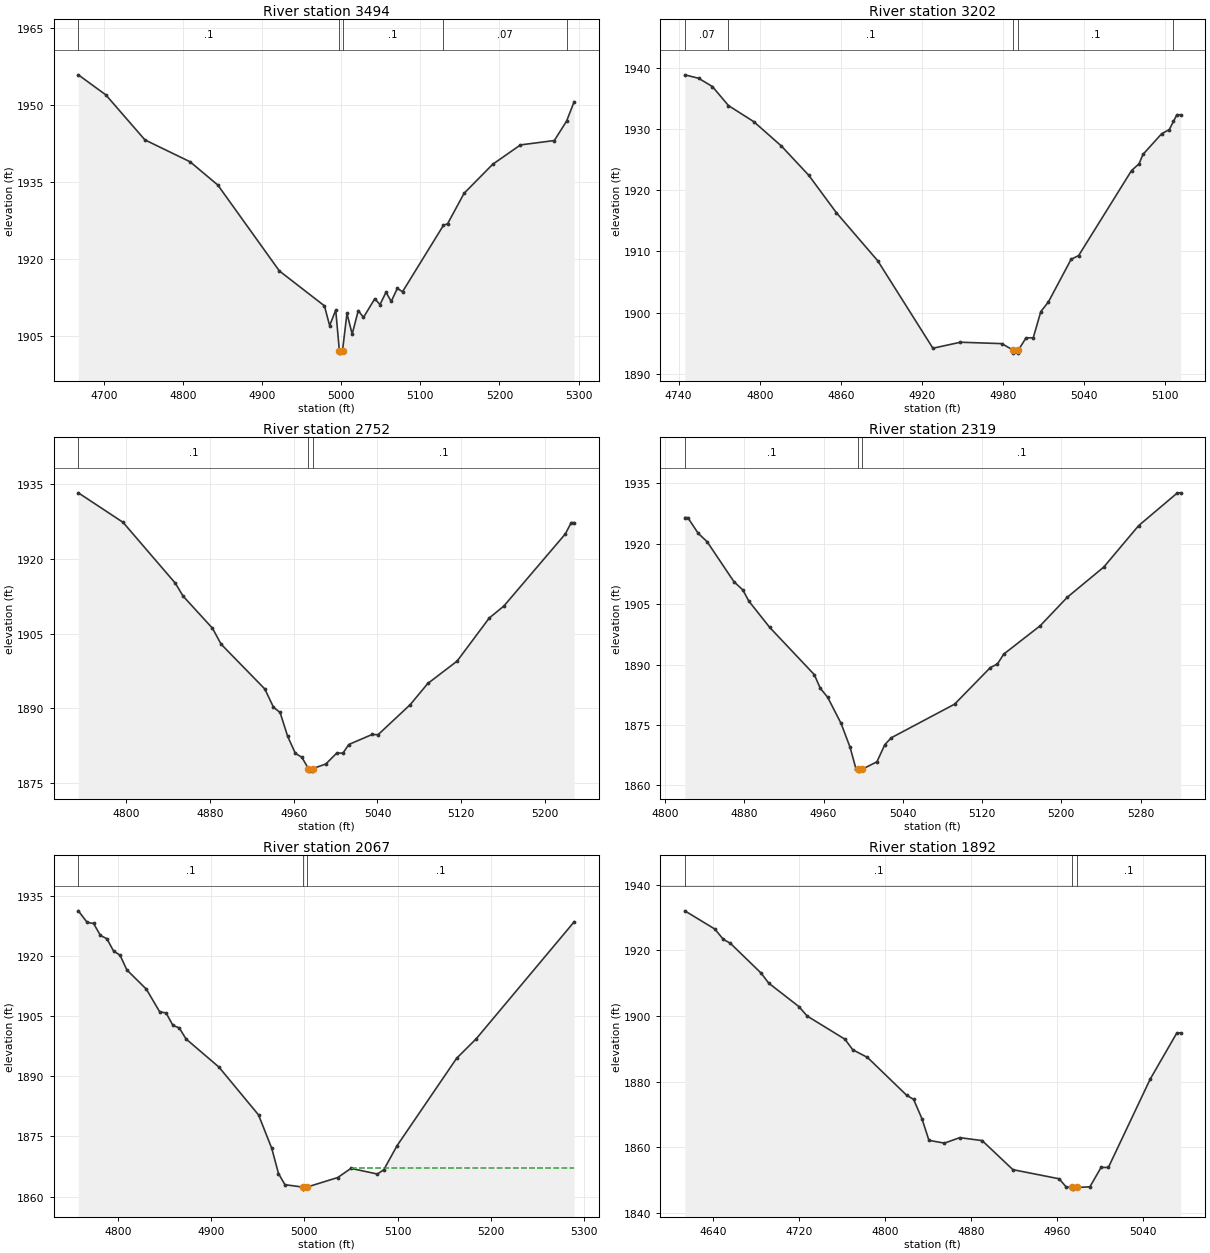
Type RM Length L Ch R = 1 ,3494    ,292,292,292
BEGIN DESCRIPTION:
Strea0328 8.0
END DESCRIPTION:
XS GIS Cut Line= 2
      1865403.64     13941465.14      1864928.59     13941055.61
#Sta/Elev= 30
  4667.3 1955.81  4702.2 1951.89  4751.5 1943.14  4808.6 1938.88  4843.7 1934.35
  4921.6 1917.61  4978.6 1910.81  4985.2 1906.96  4992.9 1909.98  4997.5  1902.1
  4997.7  1901.6  5001.5  1902.1  5007.1 1909.35  5013.7  1905.3  5021.4 1909.89
    5028 1908.56  5042.3 1912.19  5048.9 1911.06  5056.5 1913.47  5063.1 1911.66
  5070.8 1914.21  5077.4 1913.56  5129.2 1926.51  5134.4  1926.8  5155.3 1932.74
  5191.5 1938.39  5226.6 1942.16  5269.4 1943.01  5284.9 1946.79  5294.5 1950.58
#Mann= 5 ,-1 , 0
  4667.3      .1       0  4997.5     .05       0  5001.5      .1       0
  5129.2     .07       0  5284.9      .1       0
Bank Sta=4997.5,5001.5
XS Rating Curve= 0 ,0
Exp/Cntr=0.3,0.1

Type RM Length L Ch R = 1 ,3202    ,450,450,450
BEGIN DESCRIPTION:
Stream0328 7.0
END DESCRIPTION:
XS GIS Cut Line= 3
      1865424.99     13941324.97        1865375.       13941075.
      1865325.01     13940975.02
#Sta/Elev= 30
  4744.6 1938.83  4754.8 1938.27    4765 1936.92  4776.9 1933.81  4795.6 1931.19
    4816 1927.22  4836.3 1922.43  4856.7 1916.33  4887.3 1908.48  4928.1 1894.21
  4948.5 1895.19  4979.1 1894.96  4987.3 1893.91  4987.6 1893.41  4991.1 1893.41
  4991.3 1893.91    4997 1895.91  5002.3 1895.91  5007.9 1900.19  5013.5 1901.76
  5030.3 1908.72  5035.9 1909.34    5075 1923.21  5080.6 1924.32  5083.4 1925.83
  5097.3 1929.22  5102.9 1929.89    5106 1931.23  5108.5 1932.31  5111.3 1932.31
#Mann= 5 ,-1 , 0
  4744.6     .07       0  4776.9      .1       0  4987.3     .05       0
  4991.3      .1       0    5106     .07       0
Bank Sta=4987.3,4991.3
XS Rating Curve= 0 ,0
Exp/Cntr=0.3,0.1

Type RM Length L Ch R = 1 ,2752    ,433,433,433
BEGIN DESCRIPTION:
Stream0328 6.0
END DESCRIPTION:
XS GIS Cut Line= 3
      1865924.98     13941124.97        1865775.       13940925.
      1865574.97     13940824.99
#Sta/Elev= 30
  4754.3 1933.24    4797 1927.32    4847 1915.09  4854.3 1912.53  4882.4 1906.07
  4890.7 1902.86  4932.4 1893.88  4940.7 1890.22    4947 1889.16  4954.3 1884.34
  4961.6 1880.96  4967.8 1880.17  4974.1 1877.89  4974.4 1877.39  4977.9 1877.39
  4978.1 1877.89  4990.7 1878.82  5001.1 1881.01  5007.1 1881.01  5012.6 1882.73
    5035 1884.75  5040.6  1884.7  5071.3 1890.73  5088.1 1894.98  5116.1 1899.47
  5146.8 1908.12  5160.8 1910.53  5219.5    1925  5225.1 1927.26  5227.9 1927.26
#Mann= 3 ,-1 , 0
  4754.3      .1       0  4974.1     .05       0  4978.1      .1       0
Bank Sta=4974.1,4978.1
XS Rating Curve= 0 ,0
Exp/Cntr=0.3,0.1

Type RM Length L Ch R = 1 ,2319    ,252,252,252
BEGIN DESCRIPTION:
Stream0328 5.0
END DESCRIPTION:
XS GIS Cut Line= 3
        1866325.       13940925.        1866175.       13940825.
      1865975.02     13940575.03
#Sta/Elev= 30
    4820 1926.45    4823 1926.45  4833.5 1922.54  4842.5 1920.47  4869.6 1910.54
  4878.6 1908.49  4884.6 1905.74  4905.6 1899.23  4950.7 1887.49  4956.7 1884.13
  4964.2 1881.87  4977.7  1875.4  4986.8 1869.48  4992.8 1864.09  4995.3 1864.06
  4995.5 1863.56  4999.3 1864.06  5013.9 1865.88  5021.9 1870.13  5028.3 1871.82
  5092.3 1880.17  5128.3 1889.23  5135.5 1890.14  5141.9 1892.58  5178.8 1899.64
    5206 1906.68  5242.8 1914.16    5278 1924.44  5317.2 1932.58  5320.4 1932.58
#Mann= 3 ,-1 , 0
    4820      .1       0  4995.3     .05       0  4999.3      .1       0
Bank Sta=4995.3,4999.3
XS Rating Curve= 0 ,0
Exp/Cntr=0.3,0.1

Type RM Length L Ch R = 1 ,2067    ,175,175,175
BEGIN DESCRIPTION:
Mapping XS 6b7c82ce
END DESCRIPTION:
XS GIS Cut Line= 2
       1866520.1     13940823.15      1866155.37     13940436.41
#Sta/Elev= 30
  4757.6  1931.3  4767.1 1928.41    4774 1928.14  4781.3 1925.15  4788.2 1924.35
  4795.4 1921.26  4802.3 1920.24  4809.6 1916.57  4830.6 1911.74  4844.8 1906.11
  4851.7 1905.82    4859 1902.72  4865.8 1902.09  4873.1 1899.33  4908.3 1892.33
  4950.8 1880.39    4965 1872.03  4972.2 1865.76  4979.1 1862.98  4998.6 1862.37
  4998.8 1861.87  5002.6 1862.37  5035.8 1864.77  5049.9 1867.05  5078.2 1865.64
  5085.1 1866.71  5099.3  1872.7  5163.2 1894.52  5184.2 1899.38  5289.2 1928.56
#Mann= 3 ,-1 , 0
  4757.6      .1       0  4998.6     .05       0  5002.6      .1       0
#XS Ineff= 2 , 0
                         5051.16         1867.17
Permanent Ineff=
       F       F
Bank Sta=4998.6,5002.6
XS Rating Curve= 0 ,0
Exp/Cntr=0.3,0.1

Type RM Length L Ch R = 1 ,1892    ,470,470,470
BEGIN DESCRIPTION:
Stream0328 4.0
END DESCRIPTION:
XS GIS Cut Line= 3
      1866624.99     13940774.99        1866375.       13940475.
      1866325.01     13940425.01
#Sta/Elev= 30
  4613.8 1932.07  4641.8 1926.51  4649.6 1923.39  4656.1 1922.21  4684.7 1913.13
  4691.9 1910.04  4719.9 1902.92  4727.7 1900.01  4762.8 1892.96    4770 1889.76
  4783.7 1887.43  4820.1 1875.92  4826.6 1874.65  4834.4 1868.76  4840.9 1862.17
  4855.3 1861.32  4869.6 1862.99  4890.4 1862.09    4919 1853.24    4962 1850.46
  4968.5 1847.99  4974.3 1847.81  4974.6 1847.31  4978.3 1847.81  4990.6 1848.01
    5001 1853.92  5007.8 1853.92  5046.7 1880.82  5071.5 1894.89    5075 1894.89
#Mann= 3 ,-1 , 0
  4613.8      .1       0  4974.3     .05       0  4978.3      .1       0
#XS Ineff= 2 , 0
                         5001.59          1853.9
Permanent Ineff=
       F       F
Bank Sta=4974.3,4978.3
XS Rating Curve= 0 ,0
Exp/Cntr=0.3,0.1

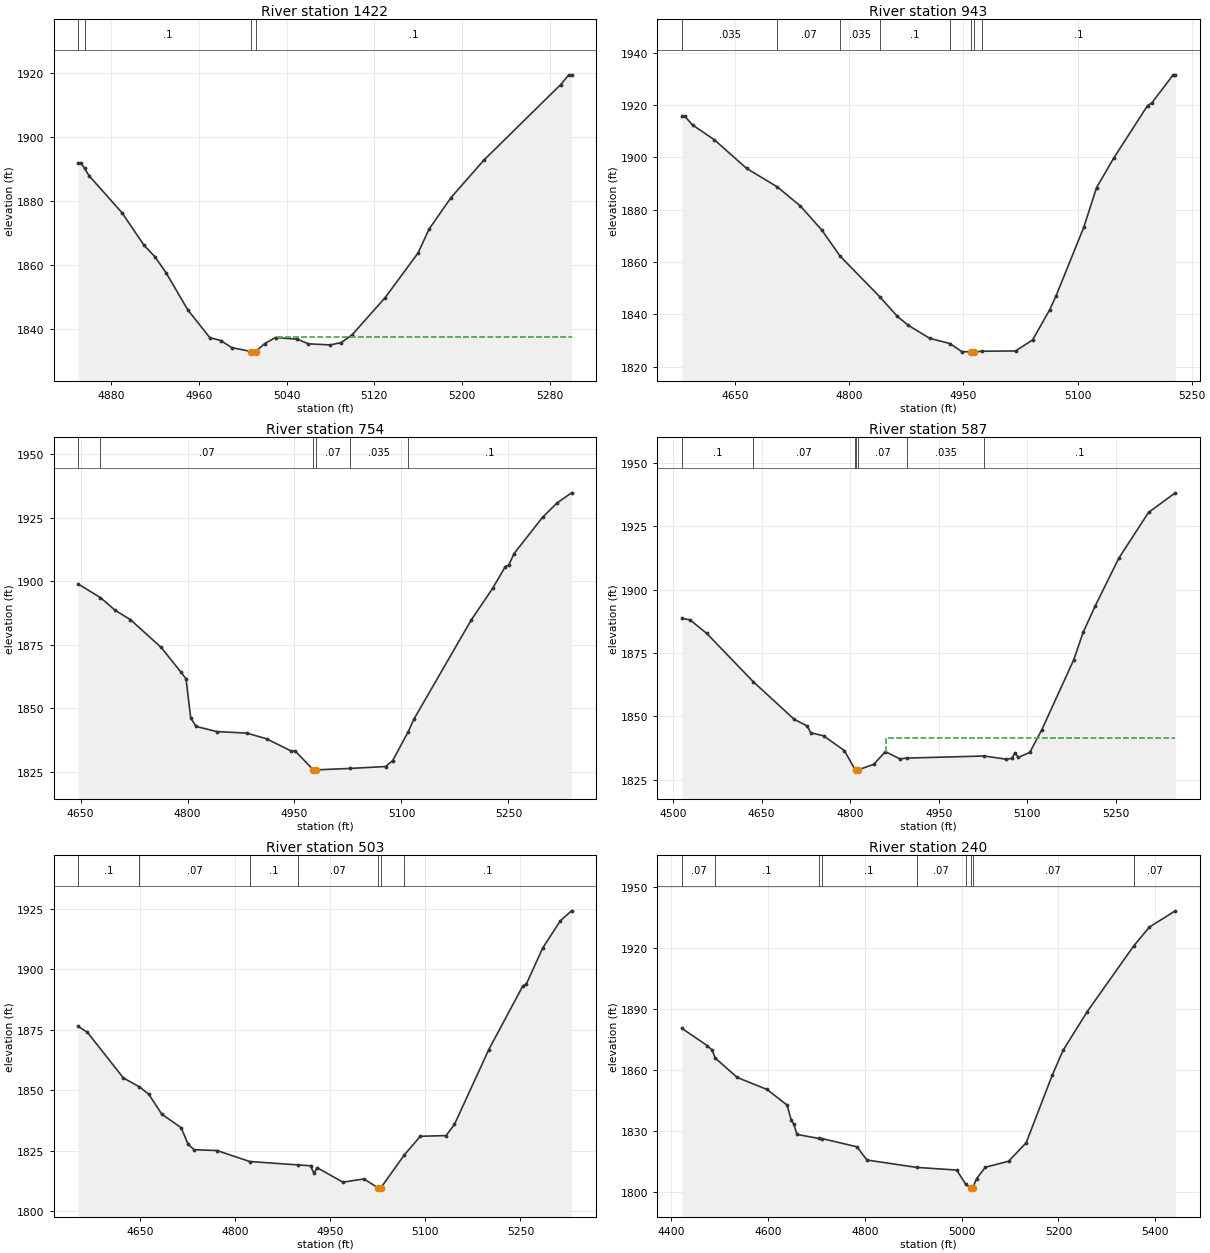
Type RM Length L Ch R = 1 ,1422    ,479,479,479
BEGIN DESCRIPTION:
Stream0328 3.0
END DESCRIPTION:
XS GIS Cut Line= 3
        1866825.     13940575.01        1866825.       13940425.
        1866825.     13940125.01
#Sta/Elev= 30
    4850 1891.95  4852.5 1891.95  4855.8 1890.15    4860 1887.85    4890 1876.27
    4910 1866.13    4920  1862.5    4930 1857.58    4950 1845.88    4970 1837.21
    4980 1836.29    4990 1834.07    5008 1832.84  5008.3 1832.34    5012 1832.84
    5020 1835.31    5030 1837.23    5050 1836.69    5060 1835.25    5080 1834.91
    5090 1835.66    5100 1838.13    5130 1849.73    5160  1863.7    5170 1871.15
    5190 1881.02    5220 1892.76    5290 1916.39  5297.5 1919.48    5300 1919.48
#Mann= 4 ,-1 , 0
    4850     .07       0  4855.8      .1       0    5008     .05       0
    5012      .1       0
#XS Ineff= 2 , 0
                         5031.91         1837.43
Permanent Ineff=
       F       F
Bank Sta=5008,5012
XS Rating Curve= 0 ,0
Exp/Cntr=0.3,0.1

Type RM Length L Ch R = 1 ,943     ,189,189,189
BEGIN DESCRIPTION:
Stream0328 2.0
END DESCRIPTION:
XS GIS Cut Line= 3
        1866975.       13940725.        1867275.       13940425.
      1867375.01     13940224.98
#Sta/Elev= 30
  4580.5 1915.79    4584 1915.79  4594.6 1912.33  4622.9 1906.75  4665.4 1895.78
  4705.7 1888.72  4736.1  1881.4  4764.4 1872.14  4788.2 1862.26  4840.5 1846.68
  4863.3 1839.29  4877.5 1835.88  4905.8 1830.87  4932.3 1828.87  4948.2 1825.76
  4960.3  1825.7  4960.6  1825.2  4964.3  1825.7  4975.2 1825.93  5018.7 1826.03
  5041.1 1830.28  5063.5 1841.79  5071.9 1847.12  5108.2 1873.26    5125  1888.4
  5147.3 1899.58    5192  1919.8  5197.6 1920.78  5225.6 1931.52  5228.4 1931.52
#Mann= 8 ,-1 , 0
  4580.5    .035       0  4705.7     .07       0  4788.2    .035       0
  4840.5      .1       0  4932.3     .07       0  4960.3     .05       0
  4964.3     .07       0  4975.2      .1       0
Bank Sta=4960.3,4964.3
XS Rating Curve= 0 ,0
Exp/Cntr=0.3,0.1

Type RM Length L Ch R = 1 ,754     ,167,167,167
BEGIN DESCRIPTION:
Mapping XS 332ab42e
END DESCRIPTION:
XS GIS Cut Line= 4
      1867191.14     13940834.35      1867387.34     13940606.49
       1867432.1     13940497.48      1867443.89     13940224.47
#Sta/Elev= 30
  4646.7 1898.91  4677.9 1893.56  4698.6 1888.55    4720 1884.86  4762.8 1874.01
    4791 1864.15  4797.9 1861.52  4804.5 1846.14  4812.2 1842.81  4840.7 1840.82
  4883.4 1840.19  4910.9 1837.96  4945.1 1833.18  4950.9 1833.18  4976.4 1825.73
  4976.6 1825.23  4980.4 1825.73  5027.4 1826.29  5077.7 1827.04  5087.7 1829.39
  5109.5 1840.75  5117.8 1845.87  5197.8 1884.73  5227.9 1897.23  5245.6 1905.74
  5250.6 1906.41  5257.9  1910.9  5297.9 1925.21    5318 1930.78  5338.5 1934.82
#Mann= 6 ,-1 , 0
  4646.7    .035       0  4677.9     .07       0  4976.4     .05       0
  4980.4     .07       0  5027.4    .035       0  5109.5      .1       0
Bank Sta=4976.4,4980.4
XS Rating Curve= 0 ,0
Exp/Cntr=0.3,0.1

Type RM Length L Ch R = 1 ,587     ,84,84,84
BEGIN DESCRIPTION:
Stream0328 1.1
END DESCRIPTION:
XS GIS Cut Line= 4
      1867300.02     13940929.07      1867548.28     13940687.75
      1867550.01       13940469.      1867522.23      13940199.9
#Sta/Elev= 30
  4515.2 1888.64  4528.7 1888.11    4557 1882.79  4635.8 1863.75  4705.4 1848.83
  4726.7 1846.31  4733.7 1843.52    4755 1842.37  4790.3 1836.52  4808.2 1829.12
  4809.6 1828.92  4809.8 1828.42  4813.6 1828.92  4839.9 1831.09  4859.8 1836.11
  4884.2 1833.26  4895.6 1833.56  5027.4 1834.39  5064.2 1833.13  5073.9 1833.44
  5078.9 1835.56  5084.8 1833.84  5104.3  1835.8  5124.4 1844.61  5178.7 1872.31
  5194.8 1883.24  5214.9 1893.48  5255.1 1912.42  5305.4 1930.46  5350.7  1938.2
#Mann= 7 ,-1 , 0
  4515.2      .1       0  4635.8     .07       0  4808.2     .07       0
  4809.6     .05       0  4813.6     .07       0  4895.6    .035       0
  5027.4      .1       0
#XS Ineff= 2 , 0
                         4861.24          1841.3
Permanent Ineff=
       F       F
Bank Sta=4809.6,4813.6
XS Rating Curve= 0 ,0
Exp/Cntr=0.3,0.1

Type RM Length L Ch R = 1 ,503     ,263,263,263
BEGIN DESCRIPTION:
Stream0328 1.0
END DESCRIPTION:
XS GIS Cut Line= 3
       1867713.2     13941014.13        1867625.       13940575.
      1867567.38     13940250.27
#Sta/Elev= 30
  4552.9 1876.38  4567.3 1873.99  4624.2 1855.08  4649.4 1851.43  4664.2 1848.38
  4684.6 1840.16  4715.2 1834.58    4726 1827.79  4735.6 1825.46  4771.8 1825.13
  4823.3  1820.6    4899 1819.21  4919.2 1818.84  4924.5 1815.68  4929.6 1818.05
  4970.2 1812.07  5003.3  1813.4  5025.8  1809.7  5026.1  1809.2  5029.8  1809.7
  5067.1 1823.36  5092.2 1831.03  5132.8 1831.31    5146 1835.92    5200 1866.74
    5254 1893.19  5259.1 1893.77  5285.2 1908.79  5313.1 1920.06  5330.6 1924.11
#Mann= 7 ,-1 , 0
  4552.9      .1       0  4649.4     .07       0  4823.3      .1       0
    4899     .07       0  5025.8     .05       0  5029.8     .07       0
  5067.1      .1       0
Bank Sta=5025.8,5029.8
XS Rating Curve= 0 ,0
Exp/Cntr=0.3,0.1

Type RM Length L Ch R = 1 ,240     ,134,134,134
BEGIN DESCRIPTION:
Stream0328 0.0
END DESCRIPTION:
XS GIS Cut Line= 4
      1867733.19     13941035.56      1867863.22      13940526.4
      1867809.79     13940292.05      1867654.73     13940090.95
#Sta/Elev= 30
  4421.7 1880.38  4473.9 1871.92  4484.2 1869.68  4490.3 1865.83  4535.8 1856.24
  4597.7  1850.3    4639 1842.65  4647.7 1835.23  4652.9 1833.21  4659.7 1828.17
  4704.6 1826.23    4711 1826.17  4783.5  1822.1  4804.1 1815.59  4906.7 1811.97
  4989.7 1810.65  5007.9 1803.82  5018.4 1801.77  5018.7 1801.27  5022.4 1801.77
  5030.7  1806.4  5048.9 1812.04    5097    1815  5133.3 1824.08  5187.1 1857.29
  5209.5 1869.55  5259.6 1888.64  5355.6 1920.96    5388 1930.23  5441.5 1938.22
#Mann= 9 ,-1 , 0
  4421.7     .07       0  4490.3      .1       0  4704.6     .07       0
    4711      .1       0  4906.7     .07       0  5007.9     .07       0
  5018.4     .05       0  5022.4     .07       0  5355.6     .07       0
Bank Sta=5018.4,5022.4
XS Rating Curve= 0 ,0
Exp/Cntr=0.3,0.1

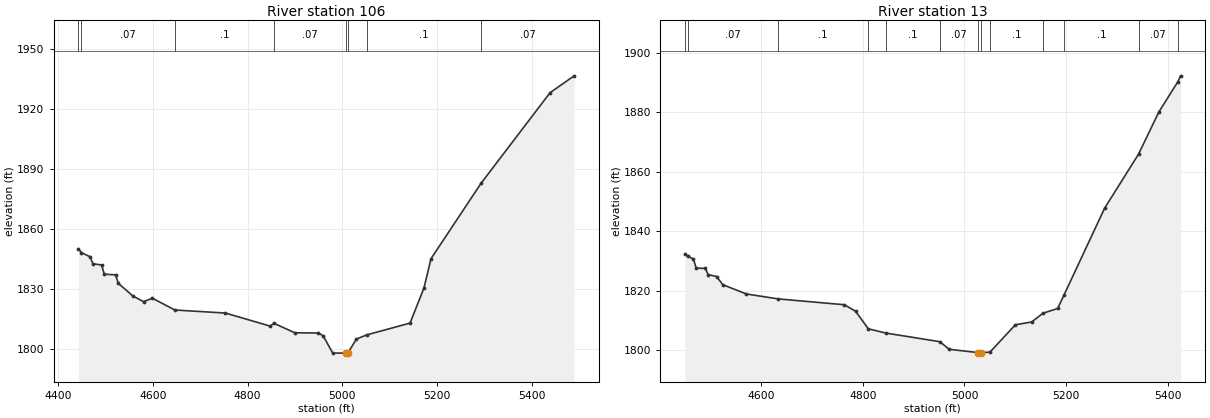
Type RM Length L Ch R = 1 ,106     ,93,93,93
BEGIN DESCRIPTION:
Stream0328 0.1
END DESCRIPTION:
XS GIS Cut Line= 4
      1867819.96     13940951.98      1867970.07     13940583.44
      1867968.61     13940357.15      1867730.12     13940009.77
#Sta/Elev= 30
  4443.1 1850.22  4449.6 1848.36  4468.3 1846.19  4473.7  1842.8  4492.3 1842.13
  4497.7 1837.57  4521.8 1837.23  4527.2 1833.04  4558.6 1826.63  4580.7 1823.86
  4599.3 1825.58  4646.7  1819.7    4753 1818.19  4847.8 1811.66  4855.4 1813.08
  4899.5 1808.35  4949.5 1808.21  4959.5 1806.81  4979.5 1798.23  5007.5 1798.19
  5007.7 1797.69  5011.5 1798.19  5029.5  1805.2  5052.1 1807.35  5142.7 1813.18
    5172 1830.71  5186.9 1845.32  5292.5 1882.96  5437.9 1928.11  5488.7 1936.52
#Mann= 8 ,-1 , 0
  4443.1      .1       0  4449.6     .07       0  4646.7      .1       0
  4855.4     .07       0  5007.5     .05       0  5011.5     .07       0
  5052.1      .1       0  5292.5     .07       0
Bank Sta=5007.5,5011.5
XS Rating Curve= 0 ,0
Exp/Cntr=0.3,0.1

Type RM Length L Ch R = 1 ,13      ,0,0,0
BEGIN DESCRIPTION:
Stream0328 0.2
END DESCRIPTION:
XS GIS Cut Line= 4
      1867861.68     13940932.19      1868063.49     13940473.89
      1868059.59      13940292.9      1867870.17     13940069.75
#Sta/Elev= 30
  4450.3 1832.38  4456.4 1831.65  4467.3 1830.74  4472.7 1827.66  4490.6 1827.61
  4496.1 1825.53  4512.8 1824.85  4524.9 1822.12  4571.5 1818.99  4633.7 1817.34
  4763.7 1815.38    4786 1813.19    4811 1807.28  4845.6 1805.86  4951.5 1802.96
    4970  1800.4  5027.5 1799.28  5027.9 1798.78  5032.4 1799.28    5050 1799.44
    5100 1808.64  5132.1 1809.59  5154.1 1812.51  5183.1 1814.12  5195.4 1818.56
  5275.4 1847.81  5342.2 1866.02  5381.9 1880.11  5419.3 1890.29  5424.8  1892.3
#Mann= 13 ,-1 , 0
  4450.3      .1       0  4456.4     .07       0  4633.7      .1       0
    4811     .07       0  4845.6      .1       0  4951.5     .07       0
  5027.5     .05       0  5032.4     .07       0    5050      .1       0
  5154.1     .07       0  5195.4      .1       0  5342.2     .07       0
  5419.3      .1       0
Bank Sta=5027.5,5032.4
XS Rating Curve= 0 ,0
Exp/Cntr=0.3,0.1

Chan Stop Cuts=-1
Use User Specified Reach Order=0
Composite Channel Slope=5