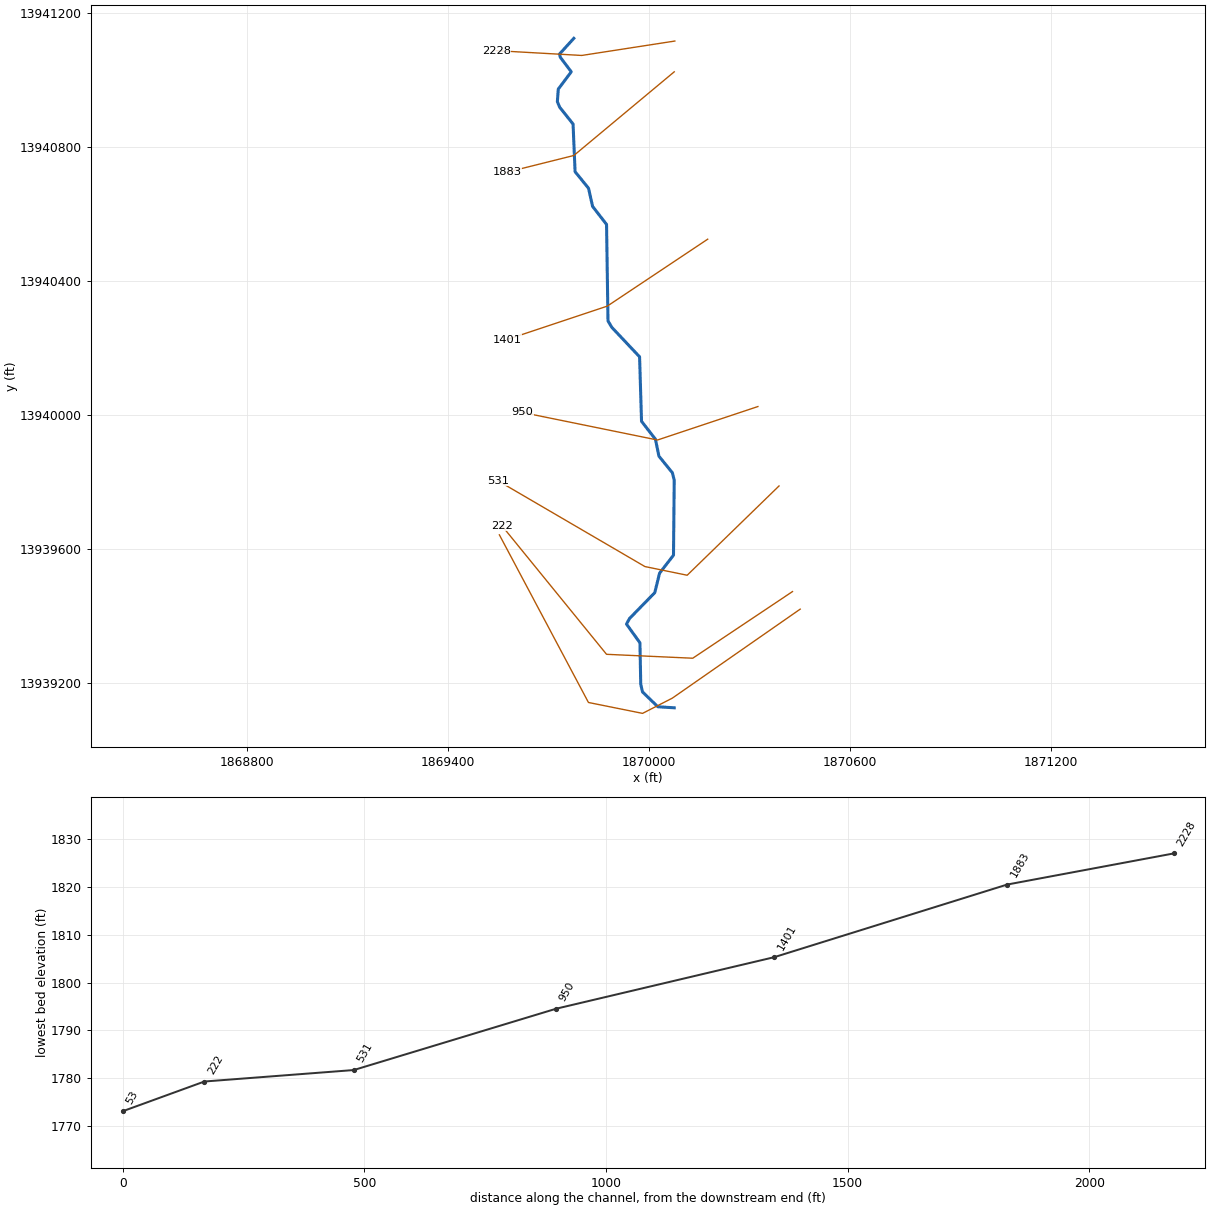
--- Stream0329.prj (project) ---

Proj Title=Stream0329 Base Level Engineering
Current Plan=p01
Default Exp/Contr=0.3,0.1
English Units
Geom File=g01
Flow File=f01
Plan File=p01
Y Axis Title=Elevation
X Axis Title(PF)=Main Channel Distance
X Axis Title(XS)=Station
BEGIN DESCRIPTION:
Stream0329
END DESCRIPTION:
DSS Export Rating Curves= 0
DSS Export Rating Curve Sorted= 0
DSS Export Volume Flow Curves= 0
DXF OffsetX= 0
DXF OffsetY= 0
DXF ScaleX= 1
DXF ScaleY= 10

--- Stream0329.p01 (plan) ---

Plan Title=Multiple Run
Short Identifier=Multiple
Geom File=g01
Flow File=f01
Subcritical Flow
K Sum by GR= 0
Std Step Tol= 0.01
Critical Tol= 0.01
Num of Std Step Trials= 20
Max Error Tol= 0.3
Flow Tol Ratio= 0.001
Split Flow NTrial= 30
Split Flow Tol= 0.02
Split Flow Ratio= 0.02
Log Output Level= 0
Friction Slope Method= 1
Unsteady Friction Slope Method= 2
Unsteady Bridges Friction Slope Method= 1
Parabolic Critical Depth
Global Vel Dist=  1 , 1 , 1
Global Log Level= 0
CheckData=True
Encroach Param= -1, 0, 0, 0
BEGIN DESCRIPTION:
Multiple Run
END DESCRIPTION:

--- Stream0329.f01 (steady flow) ---

Flow Title=Multiple
Program Version=4.10
Number of Profiles= 7
Profile Names=10-year,25-year,50-year,1pct_min,100-year,1pct_plu,500-year
River Rch & RM=Stream0329,Reach-1         ,2228
     478     777    1050     690    1377    2747    2328
Boundary for River Rch & Prof#=Stream0329,Reach-1         , 1
Up Type= 0
Dn Type= 3
Dn Slope=0.005
Boundary for River Rch & Prof#=Stream0329,Reach-1         , 2
Up Type= 0
Dn Type= 3
Dn Slope=0.005
Boundary for River Rch & Prof#=Stream0329,Reach-1         , 3
Up Type= 0
Dn Type= 3
Dn Slope=0.005
Boundary for River Rch & Prof#=Stream0329,Reach-1         , 4
Up Type= 0
Dn Type= 3
Dn Slope=0.005
Boundary for River Rch & Prof#=Stream0329,Reach-1         , 5
Up Type= 0
Dn Type= 3
Dn Slope=0.005
Boundary for River Rch & Prof#=Stream0329,Reach-1         , 6
Up Type= 0
Dn Type= 3
Dn Slope=0.005
Boundary for River Rch & Prof#=Stream0329,Reach-1         , 7
Up Type= 0
Dn Type= 3
Dn Slope=0.005
DSS Import GetInterval= 0
DSS Import GetPeak= 0
DSS Import FillOption= 0

--- Stream0329.g01 (geometry) ---

Geom Title=Existing Conditions

River Reach=Stream0329,Reach-1
Reach XY= 30
      1869775.00     13941125.00      1869732.51     13941078.34
      1869734.60     13941068.34      1869767.33     13941025.09
      1869728.59     13940973.37      1869725.81     13940935.71
      1869732.83     13940919.09      1869772.70     13940869.07
      1869778.76     13940726.56      1869818.88     13940677.18
      1869831.12     13940622.82      1869872.76     13940569.07
      1869877.07     13940280.86      1869888.40     13940261.69
      1869971.45     13940173.53      1869977.24     13939980.93
      1870018.88     13939927.18      1870029.19     13939876.74
      1870069.29     13939827.35      1870074.94     13939804.97
      1870072.76     13939580.93      1870031.14     13939527.17
      1870016.82     13939468.94      1869941.32     13939391.69
      1869932.33     13939375.10      1869972.52     13939319.14
      1869974.93     13939194.91      1869980.27     13939172.31
      1870025.98     13939128.12      1870075.00     13939125.00

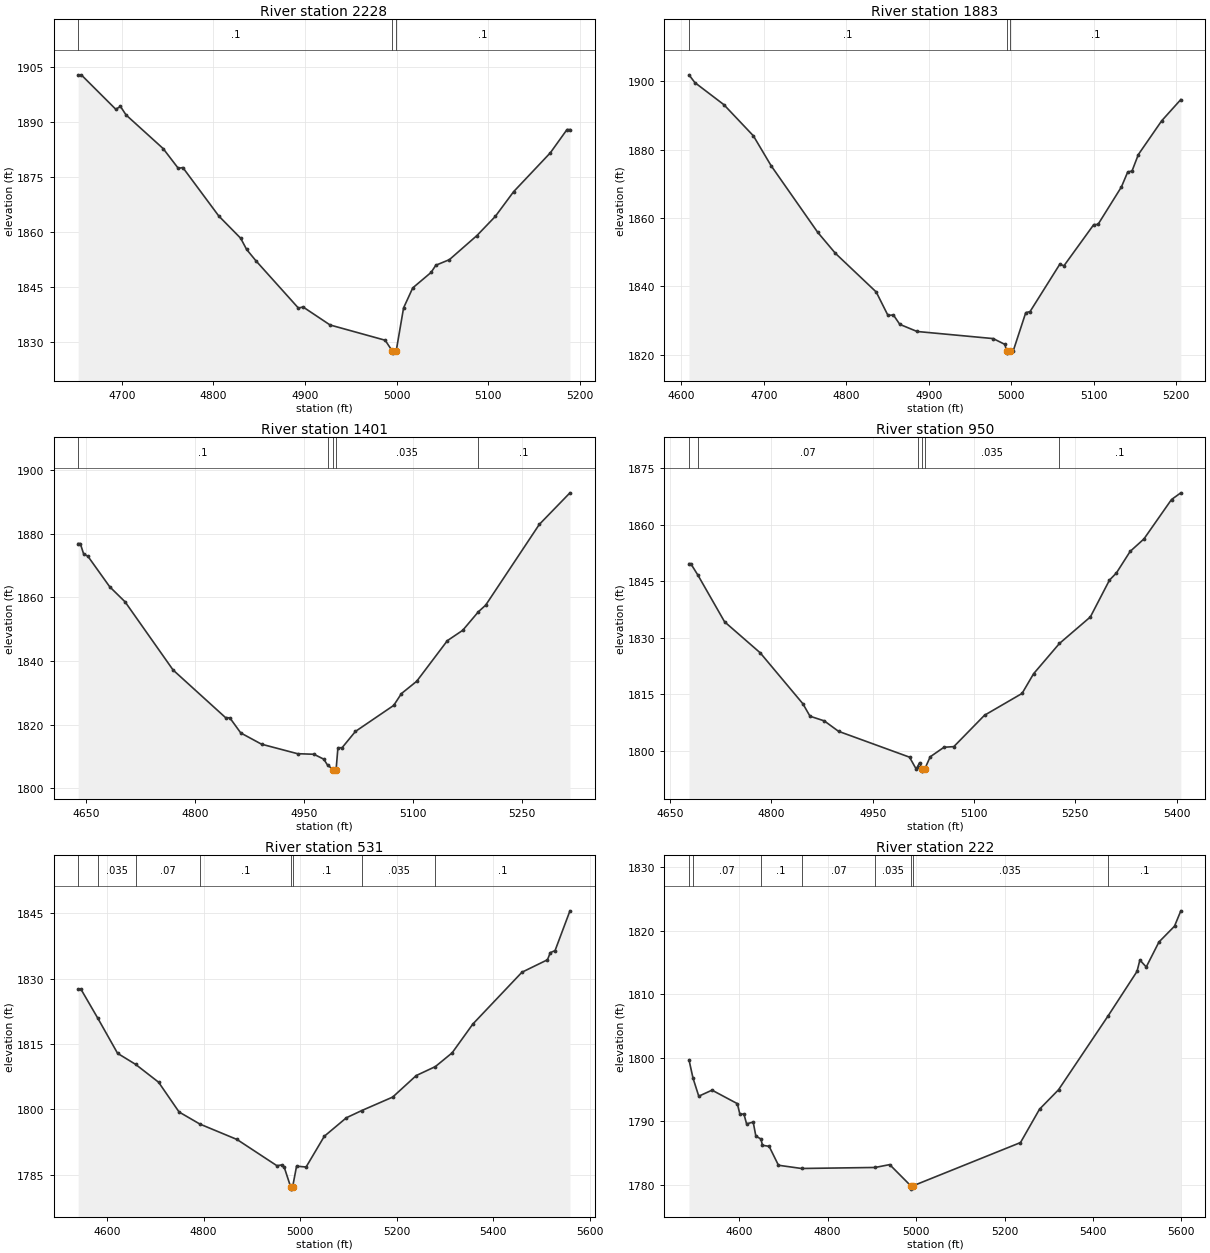
Type RM Length L Ch R = 1,2228,345,345,345
BEGIN DESCRIPTION:
Stream0329 5.0
END DESCRIPTION:
XS GIS Cut Line= 3
      1870076.73     13941116.90      1869798.65     13941073.87
      1869543.64     13941088.19
#Sta/Elev= 30
  4652.3 1903.00  4655.7 1903.00  4693.4 1893.60  4698.5 1894.37  4704.6 1892.05
  4745.1 1882.87  4761.6 1877.48  4766.6 1877.69  4805.8 1864.47  4829.7 1858.40
  4836.2 1855.34  4846.3 1852.26  4892.7 1839.34  4897.8 1839.64  4927.3 1834.72
  4987.4 1830.56  4995.4 1827.54  4995.7 1827.04  4999.4 1827.54  5007.5 1839.38
  5017.5 1844.84  5037.5 1849.06  5042.7 1851.03  5057.5 1852.55  5087.6 1859.14
  5107.6 1864.35  5127.6 1871.10  5167.7 1881.72  5185.9 1888.07  5189.1 1888.07
#Mann=3,-1,0
  4652.3     0.1       0  4995.4    0.05       0  4999.4     0.1       0
Bank Sta=4995.4,4999.4
Exp/Cntr=0.3,0.1

Type RM Length L Ch R = 1,1883,482,482,482
BEGIN DESCRIPTION:
Stream0329 4.0
END DESCRIPTION:
XS GIS Cut Line= 3
      1870074.97     13941024.98      1869775.00     13940775.00
      1869575.03     13940725.01
#Sta/Elev= 30
  4609.2 1901.86  4616.3 1899.59  4651.5 1893.14  4687.3 1884.03  4708.7 1875.34
  4765.4 1855.81  4786.8 1849.69  4836.3 1838.39  4850.6 1831.52  4857.1 1831.69
  4864.9 1828.93  4885.8 1826.85  4978.2 1824.77  4992.5 1823.06  4994.4 1821.02
  4994.7 1820.52  4998.4 1821.02  5002.3 1821.02  5017.7 1832.35  5022.9 1832.66
  5058.9 1846.47  5064.1 1846.07  5100.2 1858.09  5105.3 1858.12  5133.7 1869.08
  5141.4 1873.47  5146.6 1873.75  5154.3 1878.57  5182.6 1888.43  5205.8 1894.64
#Mann=3,-1,0
  4609.2     0.1       0  4994.4    0.05       0  4998.4     0.1       0
Bank Sta=4994.4,4998.4
Exp/Cntr=0.3,0.1

Type RM Length L Ch R = 1,1401,451,451,451
BEGIN DESCRIPTION:
Stream0329 3.0
END DESCRIPTION:
XS GIS Cut Line= 3
      1870174.98     13940524.99      1869875.00     13940325.00
      1869574.96     13940224.99
#Sta/Elev= 30
  4639.0 1876.97  4642.0 1876.97  4646.5 1873.74  4652.5 1872.95  4682.5 1863.35
  4703.6 1858.62  4769.7 1837.15  4841.8 1822.18  4847.8 1822.08  4862.8 1817.34
  4891.4 1813.80  4940.9 1810.81  4963.5 1810.63  4977.0 1809.08  4982.4 1807.16
  4990.0 1805.82  4990.3 1805.32  4994.0 1805.82  4996.5 1812.69  5002.2 1812.69
  5020.6 1817.82  5073.3 1826.02  5083.9 1829.74  5104.9 1833.61  5147.1 1846.40
  5168.2 1849.65  5189.9 1855.52  5199.8 1857.57  5273.6 1882.99  5315.8 1892.94
#Mann=5,-1,0
  4639.0     0.1       0  4982.4   0.035       0  4990.0   0.035       0
  4994.0   0.035       0  5189.9     0.1       0
Bank Sta=4990,4994
Exp/Cntr=0.3,0.1

Type RM Length L Ch R = 1,950,419,419,419
BEGIN DESCRIPTION:
Stream0329 2.0
END DESCRIPTION:
XS GIS Cut Line= 3
      1870324.95     13940024.98      1870025.00     13939925.00
      1869621.49     13940007.32
#Sta/Elev= 30
  4678.1 1849.66  4680.7 1849.66  4691.2 1846.63  4730.8 1834.20  4783.5 1825.97
  4846.7 1812.43  4857.2 1809.13  4878.3 1807.89  4899.4 1805.12  5004.5 1798.25
  5014.4 1795.08  5016.4 1795.75  5019.5 1796.79  5022.9 1795.04  5023.1 1794.54
  5026.9 1795.04  5035.1 1798.34  5055.5 1800.88  5070.1 1801.05  5115.5 1809.38
  5171.1 1815.18  5188.2 1820.42  5226.4 1828.45  5272.2 1835.50  5300.5 1845.29
  5310.7 1847.17  5331.1 1852.91  5351.5 1856.22  5392.3 1866.69  5406.1 1868.47
#Mann=6,-1,0
  4678.1     0.1       0  4691.2    0.07       0  5016.4   0.035       0
  5022.9    0.05       0  5026.9   0.035       0  5226.4     0.1       0
Bank Sta=5022.9,5026.9
Exp/Cntr=0.3,0.1

Type RM Length L Ch R = 1,531,309,309,309
BEGIN DESCRIPTION:
Stream0329 1.0
END DESCRIPTION:
XS GIS Cut Line= 4
      1870388.00     13939787.72      1870113.62     13939521.00
      1869987.37     13939546.97      1869548.86     13939802.95
#Sta/Elev= 30
  4540.0 1827.62  4545.6 1827.62  4580.8 1820.91  4621.8 1812.86  4659.2 1810.32
  4706.7 1806.24  4749.2 1799.40  4792.5 1796.62  4869.3 1793.09  4951.9 1787.08
  4962.1 1787.25  4967.2 1786.70  4980.5 1782.20  4980.7 1781.70  4984.5 1782.20
  4992.7 1786.96  5012.5 1786.78  5050.2 1793.83  5096.0 1798.08  5127.6 1799.72
  5191.9 1802.82  5240.7 1807.76  5280.4 1809.82  5315.1 1812.97  5358.1 1819.59
  5459.8 1831.47  5512.7 1834.33  5518.5 1835.96  5528.4 1836.43  5559.3 1845.56
#Mann=8,-1,0
  4540.0    0.07       0  4580.8   0.035       0  4659.2    0.07       0
  4792.5     0.1       0  4980.5    0.05       0  4984.5     0.1       0
  5127.6   0.035       0  5280.4     0.1       0
Bank Sta=4980.5,4984.5
Exp/Cntr=0.3,0.1

Type RM Length L Ch R = 1,222,169,169,169
BEGIN DESCRIPTION:
Stream0329 0.0
END DESCRIPTION:
XS GIS Cut Line= 4
      1870428.35     13939472.26      1870130.28     13939273.10
      1869872.73     13939284.80      1869559.67     13939669.52
#Sta/Elev= 30
  4486.4 1799.65  4495.5 1796.77  4508.5 1793.93  4538.5 1794.88  4595.6 1792.76
  4601.6 1791.08  4610.6 1791.13  4616.6 1789.58  4631.6 1789.85  4637.6 1787.65
  4649.0 1787.19  4652.6 1786.20  4667.6 1786.04  4688.7 1783.06  4740.9 1782.55
  4907.3 1782.71  4940.3 1783.16  4988.3 1779.80  4988.6 1779.30  4992.3 1779.80
  5236.1 1786.63  5279.2 1791.89  5322.1 1794.94  5434.4 1806.59  5499.6 1813.57
  5506.1 1815.36  5520.5 1814.27  5549.2 1818.20  5584.4 1820.69  5598.7 1823.11
#Mann=8,-1,0
  4486.4   0.035       0  4495.5    0.07       0  4649.0     0.1       0
  4740.9    0.07       0  4907.3   0.035       0  4988.3   0.035       0
  4992.3   0.035       0  5434.4     0.1       0
Bank Sta=4988.3,4992.3
Exp/Cntr=0.3,0.1

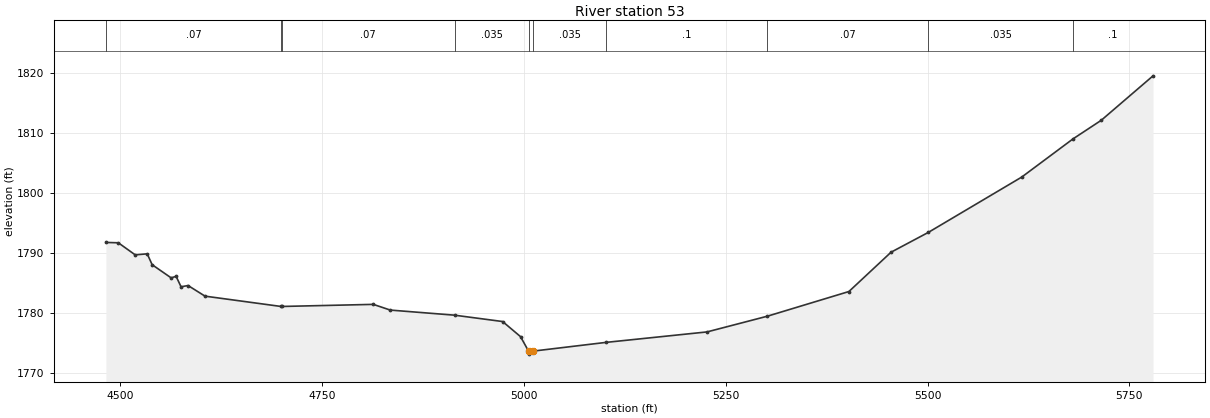
Type RM Length L Ch R = 1,53,0,0,0
BEGIN DESCRIPTION:
Stream0329 0.1
END DESCRIPTION:
XS GIS Cut Line= 5
      1870451.29     13939419.75      1870069.35     13939153.91
      1869980.37     13939108.34      1869818.69     13939140.89
      1869552.63     13939641.66
#Sta/Elev= 30
  4482.0 1791.69  4497.4 1791.63  4518.3 1789.62  4533.2 1789.79  4539.3 1787.98
  4562.8 1785.79  4569.0 1786.04  4575.1 1784.30  4583.8 1784.51  4604.8 1782.74
  4699.1 1781.02  4699.8 1781.02  4813.3 1781.37  4834.3 1780.42  4913.9 1779.57
  4973.5 1778.51  4995.7 1775.99  5005.6 1773.58  5006.1 1773.08  5011.2 1773.58
  5101.8 1775.04  5226.7 1776.78  5301.5 1779.40  5402.5 1783.51  5454.7 1790.06
  5501.0 1793.37  5616.6 1802.58  5680.1 1808.94  5715.1 1812.04  5779.3 1819.45
#Mann=10,-1,0
  4482.0    0.07       0  4699.1     0.1       0  4699.8    0.07       0
  4913.9   0.035       0  5005.6   0.035       0  5011.2   0.035       0
  5101.8     0.1       0  5301.5    0.07       0  5501.0   0.035       0
  5680.1     0.1       0
Bank Sta=5005.6,5011.2
Exp/Cntr=0.3,0.1

Chan Stop Cuts=-1