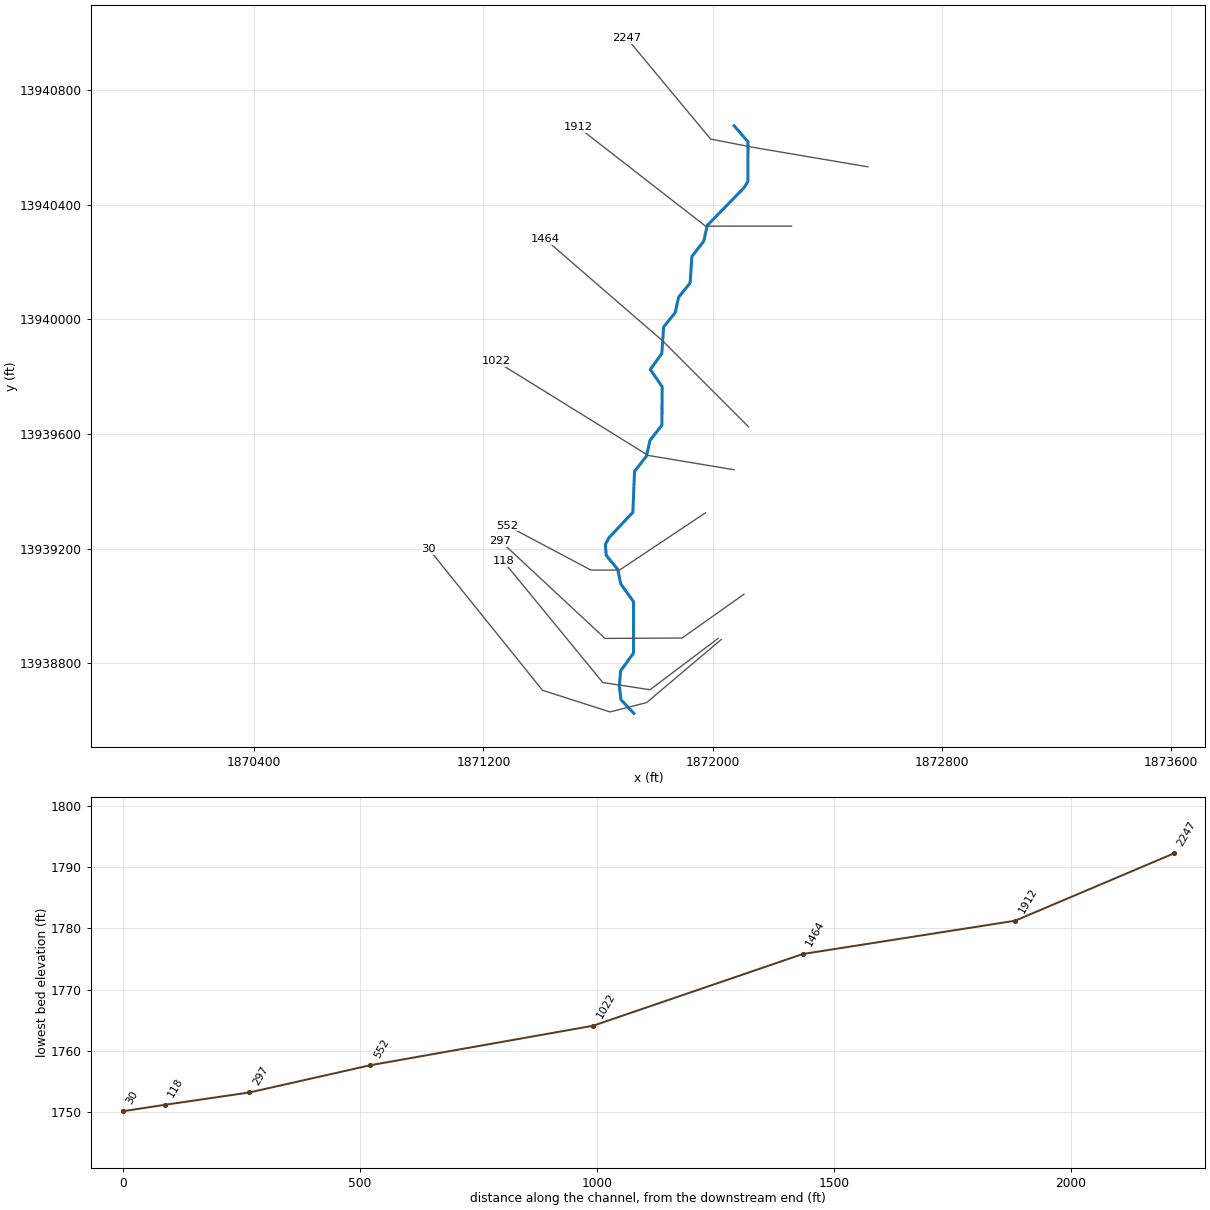
--- Stream0330.prj (project) ---

Proj Title=Stream0330 Base Level Engineering
Current Plan=p01
Default Exp/Contr=0.3,0.1
English Units
Geom File=g01
Flow File=f01
Plan File=p01
BEGIN DESCRIPTION:
Stream0330
END DESCRIPTION:

--- Stream0330.p01 (plan) ---

Plan Title=Multiple Run
Short Identifier=Multiple
Geom File=g01
Flow File=f01
Subcritical Flow
K Sum by GR= 0
Std Step Tol= 0.01
Critical Tol= 0.01
Num of Std Step Trials= 20
Max Error Tol= 0.3
Flow Tol Ratio= 0.001
Split Flow NTrial= 30
Split Flow Tol= 0.02
Split Flow Ratio= 0.02
Log Output Level= 0
Friction Slope Method= 1
Unsteady Friction Slope Method= 2
Unsteady Bridges Friction Slope Method= 1
Parabolic Critical Depth
Global Vel Dist=  1 , 1 , 1
Global Log Level= 0
CheckData=True
Encroach Param= -1, 0, 0, 0
BEGIN DESCRIPTION:
Multiple Run
END DESCRIPTION:

--- Stream0330.f01 (steady flow) ---

Flow Title=Multiple
Number of Profiles=7
Profile Names=10-year,25-year,50-year,1pct_min,100-year,1pct_plu,500-year
River Rch & RM= Stream0330,Reach-1,2247
     932    1587    2210    1491    2975    5936    5317
River Rch & RM= Stream0330,Reach-1,30
    2704    4855    7002    4867    9711   19375   18474
Boundary for River Rch & Prof#=Stream0330,Reach-1,1
Up Type=0
Dn Type=3
Dn Slope=0.005
Boundary for River Rch & Prof#=Stream0330,Reach-1,2
Up Type=0
Dn Type=3
Dn Slope=0.005
Boundary for River Rch & Prof#=Stream0330,Reach-1,3
Up Type=0
Dn Type=3
Dn Slope=0.005
Boundary for River Rch & Prof#=Stream0330,Reach-1,4
Up Type=0
Dn Type=3
Dn Slope=0.005
Boundary for River Rch & Prof#=Stream0330,Reach-1,5
Up Type=0
Dn Type=3
Dn Slope=0.005
Boundary for River Rch & Prof#=Stream0330,Reach-1,6
Up Type=0
Dn Type=3
Dn Slope=0.005
Boundary for River Rch & Prof#=Stream0330,Reach-1,7
Up Type=0
Dn Type=3
Dn Slope=0.005

--- Stream0330.g01 (geometry) ---

Geom Title=Existing Conditions

River Reach=Stream0330,Reach-1
Reach XY= 30
      1872075.00     13940675.00      1872123.12     13940619.21
      1872122.96     13940480.85      1872108.57     13940458.24
      1871980.83     13940327.30      1871968.86     13940272.83
      1871927.33     13940219.03      1871921.17     13940126.58
      1871881.11     13940077.18      1871868.89     13940022.82
      1871828.82     13939973.41      1871822.45     13939880.89
      1871782.56     13939825.00      1871823.63     13939764.56
      1871822.77     13939630.93      1871781.12     13939577.18
      1871768.88     13939522.82      1871727.25     13939469.07
      1871721.44     13939326.47      1871638.15     13939238.20
      1871625.60     13939214.37      1871628.31     13939176.74
      1871668.84     13939127.20      1871679.19     13939076.74
      1871723.80     13939014.50      1871723.78     13938835.50
      1871678.70     13938773.41      1871674.19     13938720.01
      1871680.05     13938672.45      1871725.00     13938625.00

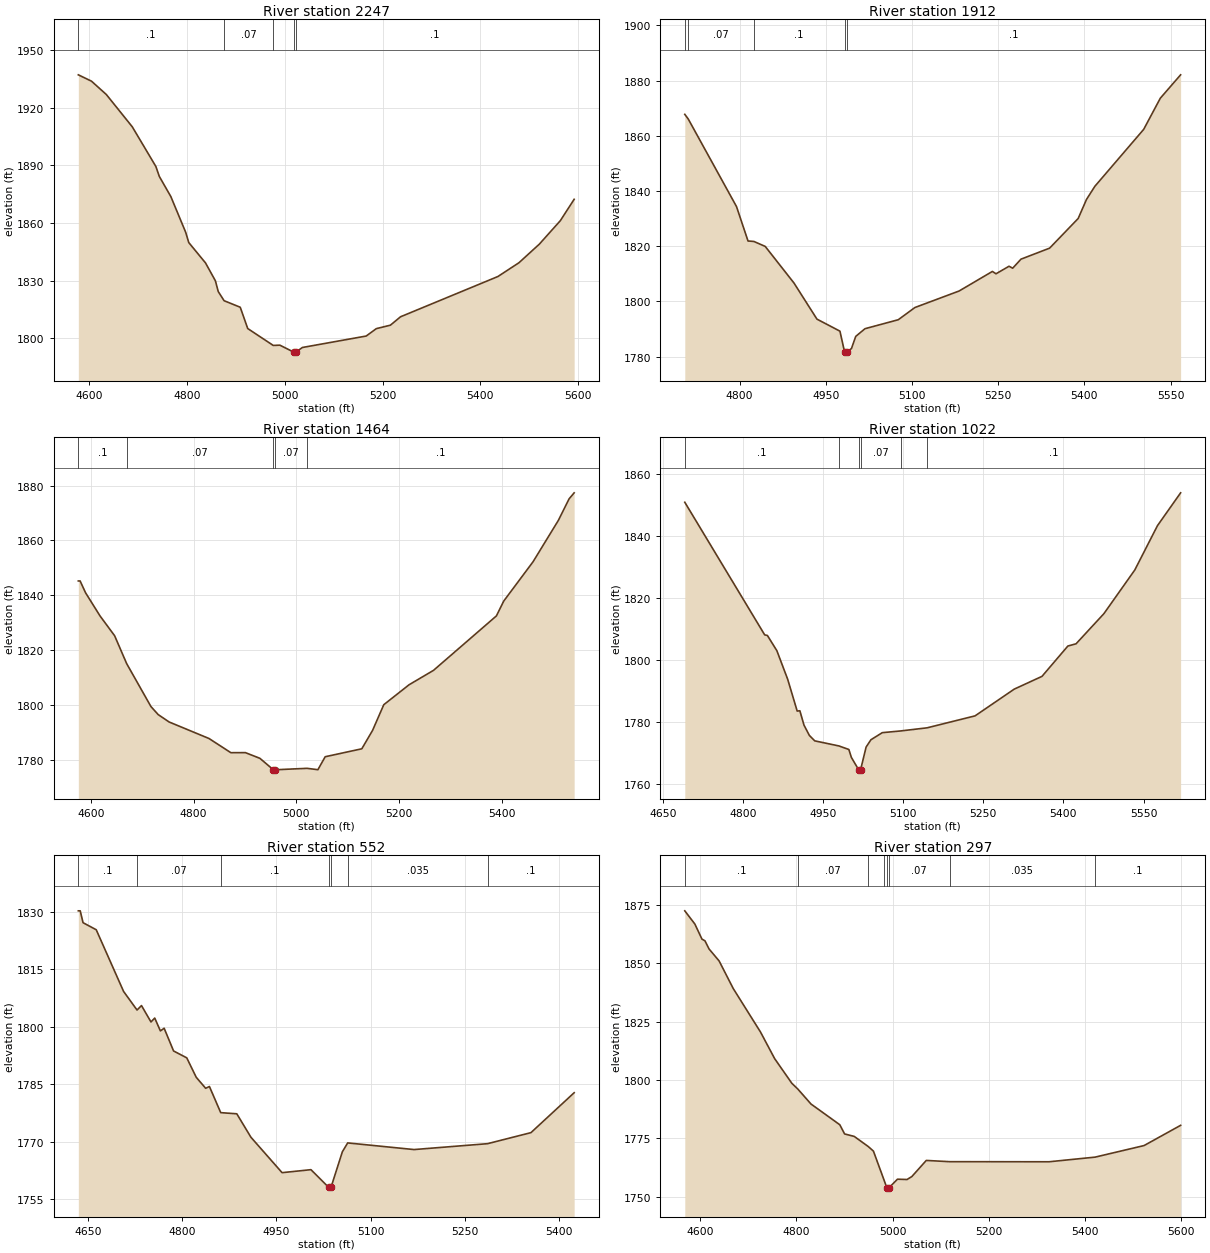
Type RM Length L Ch R = 1,2247,335,335,335
BEGIN DESCRIPTION:
Stream0330 5.0
END DESCRIPTION:
XS GIS Cut Line= 4
      1872541.49     13940532.01      1872144.51     13940599.36
      1871992.64     13940628.94      1871700.76     13940980.35
#Sta/Elev= 30
  4577.6 1937.14  4604.5 1933.84  4634.9 1926.88  4687.9 1910.09  4736.3 1889.37
  4743.2 1884.26  4766.8 1873.76  4797.2 1855.14  4803.5 1849.79  4837.8 1839.18
  4858.0 1829.86  4863.8 1824.28  4875.8 1819.51  4908.8 1816.11  4924.1 1805.02
  4976.3 1796.23  4989.9 1796.36  5018.5 1792.72  5018.8 1792.22  5022.5 1792.72
  5035.8 1795.15  5166.4 1801.12  5187.2 1804.98  5215.9 1806.77  5236.7 1811.15
  5435.9 1832.12  5478.9 1839.29  5520.5 1848.95  5563.5 1861.18  5591.8 1872.33
#Mann=5,-1,0
  4577.6     0.1       0  4875.8    0.07       0  4976.3     0.1       0
  5018.5    0.05       0  5022.5     0.1       0
Bank Sta=5018.5,5022.5
Exp/Cntr=0.3,0.1

Type RM Length L Ch R = 1,1912,448,448,448
BEGIN DESCRIPTION:
Stream0330 4.0
END DESCRIPTION:
XS GIS Cut Line= 3
      1872275.03     13940325.00      1871975.00     13940325.00
      1871530.65     13940670.51
#Sta/Elev= 30
  4704.7 1867.76  4710.6 1866.11  4794.7 1834.34  4814.7 1821.87  4824.9 1821.71
  4844.7 1819.90  4894.7 1806.65  4934.7 1793.56  4974.7 1789.20  4982.7 1781.74
  4983.0 1781.24  4986.7 1781.74  4994.7 1782.88  5002.2 1787.31  5018.3 1790.09
  5076.2 1793.34  5105.2 1797.77  5182.1 1803.75  5240.0 1810.84  5246.3 1809.99
  5269.0 1812.72  5275.3 1812.01  5289.8 1815.29  5339.6 1819.28  5389.3 1830.02
  5403.8 1836.93  5418.3 1841.67  5503.3 1862.31  5532.3 1873.62  5567.6 1882.08
#Mann=5,-1,0
  4704.7     0.1       0  4710.6    0.07       0  4824.9     0.1       0
  4982.7    0.05       0  4986.7     0.1       0
Bank Sta=4982.7,4986.7
Exp/Cntr=0.3,0.1

Type RM Length L Ch R = 1,1464,442,442,442
BEGIN DESCRIPTION:
Stream0330 3.0
END DESCRIPTION:
XS GIS Cut Line= 3
      1872124.99     13939625.01      1871825.00     13939925.00
      1871415.73     13940279.20
#Sta/Elev= 30
  4575.7 1845.20  4579.2 1845.20  4589.8 1840.88  4618.1 1832.40  4646.4 1825.21
  4669.8 1815.05  4717.1 1799.37  4731.2 1796.44  4752.5 1793.74  4830.2 1787.71
  4872.7 1782.54  4901.0 1782.56  4929.2 1780.49  4955.5 1776.31  4955.8 1775.81
  4959.5 1776.31  5021.1 1776.83  5042.2 1776.33  5056.4 1781.06  5127.7 1783.96
  5148.6 1790.65  5170.5 1800.05  5219.8 1807.33  5267.4 1812.59  5389.8 1832.45
  5404.1 1837.87  5461.1 1852.19  5510.5 1867.32  5531.3 1875.15  5541.2 1877.36
#Mann=5,-1,0
  4575.7     0.1       0  4669.8    0.07       0  4955.5    0.05       0
  4959.5    0.07       0  5021.1     0.1       0
Bank Sta=4955.5,4959.5
Exp/Cntr=0.3,0.1

Type RM Length L Ch R = 1,1022,470,470,470
BEGIN DESCRIPTION:
Stream0330 2.0
END DESCRIPTION:
XS GIS Cut Line= 3
      1872075.02     13939475.00      1871775.00     13939525.00
      1871244.45     13939853.55
#Sta/Elev= 30
  4691.2 1851.02  4840.8 1808.15  4845.8 1807.98  4863.6 1803.03  4883.8 1793.81
  4901.6 1783.53  4906.6 1783.63  4914.3 1779.01  4924.4 1775.66  4934.5 1773.90
  4979.5 1772.27  4998.3 1771.12  5003.0 1768.58  5016.4 1764.62  5016.7 1764.12
  5020.4 1764.62  5030.6 1771.90  5039.7 1774.27  5060.9 1776.55  5095.4 1777.11
  5144.9 1778.12  5234.6 1781.98  5307.9 1790.62  5359.9 1794.75  5408.3 1804.55
  5423.7 1805.28  5475.7 1815.00  5533.6 1829.13  5576.1 1843.47  5619.4 1854.07
#Mann=6,-1,0
  4691.2     0.1       0  4979.5    0.07       0  5016.4    0.05       0
  5020.4    0.07       0  5095.4   0.035       0  5144.9     0.1       0
Bank Sta=5016.4,5020.4
Exp/Cntr=0.3,0.1

Type RM Length L Ch R = 1,552,255,255,255
BEGIN DESCRIPTION:
Stream0330 1.0
END DESCRIPTION:
XS GIS Cut Line= 4
      1871974.98     13939324.99      1871675.00     13939125.00
      1871575.00     13939125.00      1871284.22     13939279.28
#Sta/Elev= 30
  4634.4 1830.20  4637.4 1830.20  4641.9 1827.11  4662.9 1825.27  4706.5 1809.19
  4727.9 1804.35  4735.0 1805.51  4750.1 1801.24  4756.1 1802.26  4765.1 1798.91
  4771.1 1799.60  4786.1 1793.68  4807.1 1791.89  4822.2 1786.82  4837.2 1783.96
  4843.2 1784.42  4861.2 1777.61  4886.8 1777.31  4909.3 1771.20  4958.9 1761.97
  5004.9 1762.75  5032.9 1758.18  5033.2 1757.68  5036.9 1758.18  5054.9 1767.40
  5063.4 1769.72  5169.1 1767.99  5286.1 1769.52  5355.3 1772.40  5424.1 1782.80
#Mann=7,-1,0
  4634.4     0.1       0  4727.9    0.07       0  4861.2     0.1       0
  5032.9    0.05       0  5036.9     0.1       0  5063.4   0.035       0
  5286.1     0.1       0
Bank Sta=5032.9,5036.9
Exp/Cntr=0.3,0.1

Type RM Length L Ch R = 1,297,179,179,179
BEGIN DESCRIPTION:
Stream0330 0.0
END DESCRIPTION:
XS GIS Cut Line= 4
      1872109.11     13939040.69      1871893.12     13938887.86
      1871624.37     13938886.50      1871259.25     13939226.42
#Sta/Elev= 30
  4567.6 1872.38  4588.6 1866.71  4603.3 1860.27  4609.5 1859.56  4618.1 1856.05
  4639.0 1850.94  4668.6 1839.06  4725.2 1820.50  4754.7 1809.09  4790.4 1798.57
  4803.1 1796.04  4830.3 1789.68  4890.3 1780.80  4900.3 1776.86  4920.3 1775.81
  4949.7 1771.45  4960.3 1769.51  4982.0 1757.34  4988.3 1753.74  4988.6 1753.24
  4992.3 1753.74  5010.3 1757.49  5030.3 1757.36  5040.3 1758.63  5070.3 1765.52
  5119.0 1764.99  5325.9 1764.95  5421.8 1766.94  5523.7 1771.89  5599.8 1780.55
#Mann=8,-1,0
  4567.6     0.1       0  4803.1    0.07       0  4949.7     0.1       0
  4982.0    0.07       0  4988.3    0.05       0  4992.3    0.07       0
  5119.0   0.035       0  5421.8     0.1       0
Bank Sta=4988.3,4992.3
Exp/Cntr=0.3,0.1

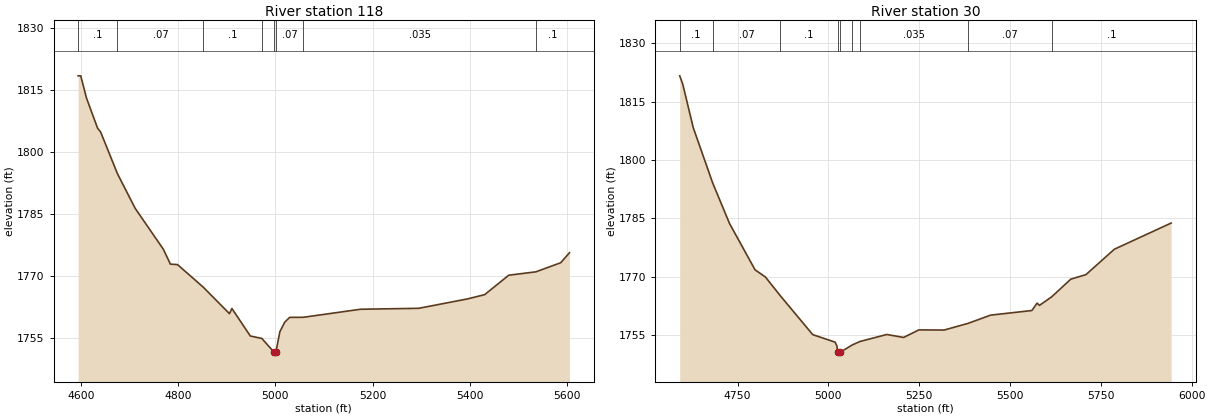
Type RM Length L Ch R = 1,118,88,88,88
BEGIN DESCRIPTION:
Stream0330 0.1
END DESCRIPTION:
XS GIS Cut Line= 4
      1872018.80     13938886.45      1871781.27     13938707.51
      1871616.42     13938732.68      1871269.83     13939155.53
#Sta/Elev= 30
  4594.3 1818.39  4599.7 1818.39  4611.6 1813.01  4634.3 1805.77  4640.6 1804.84
  4675.3 1794.75  4711.7 1786.41  4769.7 1776.52  4784.2 1772.94  4798.8 1772.83
  4851.6 1767.40  4905.7 1760.98  4910.7 1762.23  4948.6 1755.59  4972.2 1755.01
  4997.2 1751.72  4997.4 1751.22  5001.2 1751.72  5009.3 1756.62  5019.4 1758.94
  5029.5 1760.09  5057.5 1760.11  5175.2 1762.05  5295.0 1762.28  5395.5 1764.55
  5430.7 1765.58  5480.2 1770.27  5535.9 1771.08  5587.1 1773.28  5605.2 1775.71
#Mann=8,-1,0
  4594.3     0.1       0  4675.3    0.07       0  4851.6     0.1       0
  4972.2    0.07       0  4997.2    0.05       0  5001.2    0.07       0
  5057.5   0.035       0  5535.9     0.1       0
Bank Sta=4997.2,5001.2
Exp/Cntr=0.3,0.1

Type RM Length L Ch R = 1,30,0,0,0
BEGIN DESCRIPTION:
Stream0330 0.2
END DESCRIPTION:
XS GIS Cut Line= 5
      1872029.85     13938882.68      1871769.40     13938662.61
      1871641.79     13938630.05      1871406.12     13938705.57
      1871009.48     13939198.44
#Sta/Elev= 30
  4590.7 1821.61  4599.2 1819.42  4627.8 1808.34  4681.4 1794.12  4727.9 1783.69
  4798.1 1771.82  4826.7 1769.97  4866.7 1765.27  4956.9 1755.18  5018.4 1753.26
  5023.5 1752.26  5025.6 1750.68  5026.1 1750.18  5032.6 1750.68  5066.1 1752.56
  5086.4 1753.41  5160.6 1755.22  5207.0 1754.46  5249.0 1756.40  5318.6 1756.36
  5385.3 1758.10  5446.6 1760.19  5560.1 1761.37  5574.5 1763.27  5581.0 1762.69
  5614.7 1764.89  5667.3 1769.42  5708.9 1770.58  5787.3 1777.11  5943.5 1783.82
#Mann=9,-1,0
  4590.7     0.1       0  4681.4    0.07       0  4866.7     0.1       0
  5025.6    0.05       0  5032.6     0.1       0  5066.1    0.07       0
  5086.4   0.035       0  5385.3    0.07       0  5614.7     0.1       0
Bank Sta=5025.6,5032.6
Exp/Cntr=0.3,0.1

Chan Stop Cuts=-1