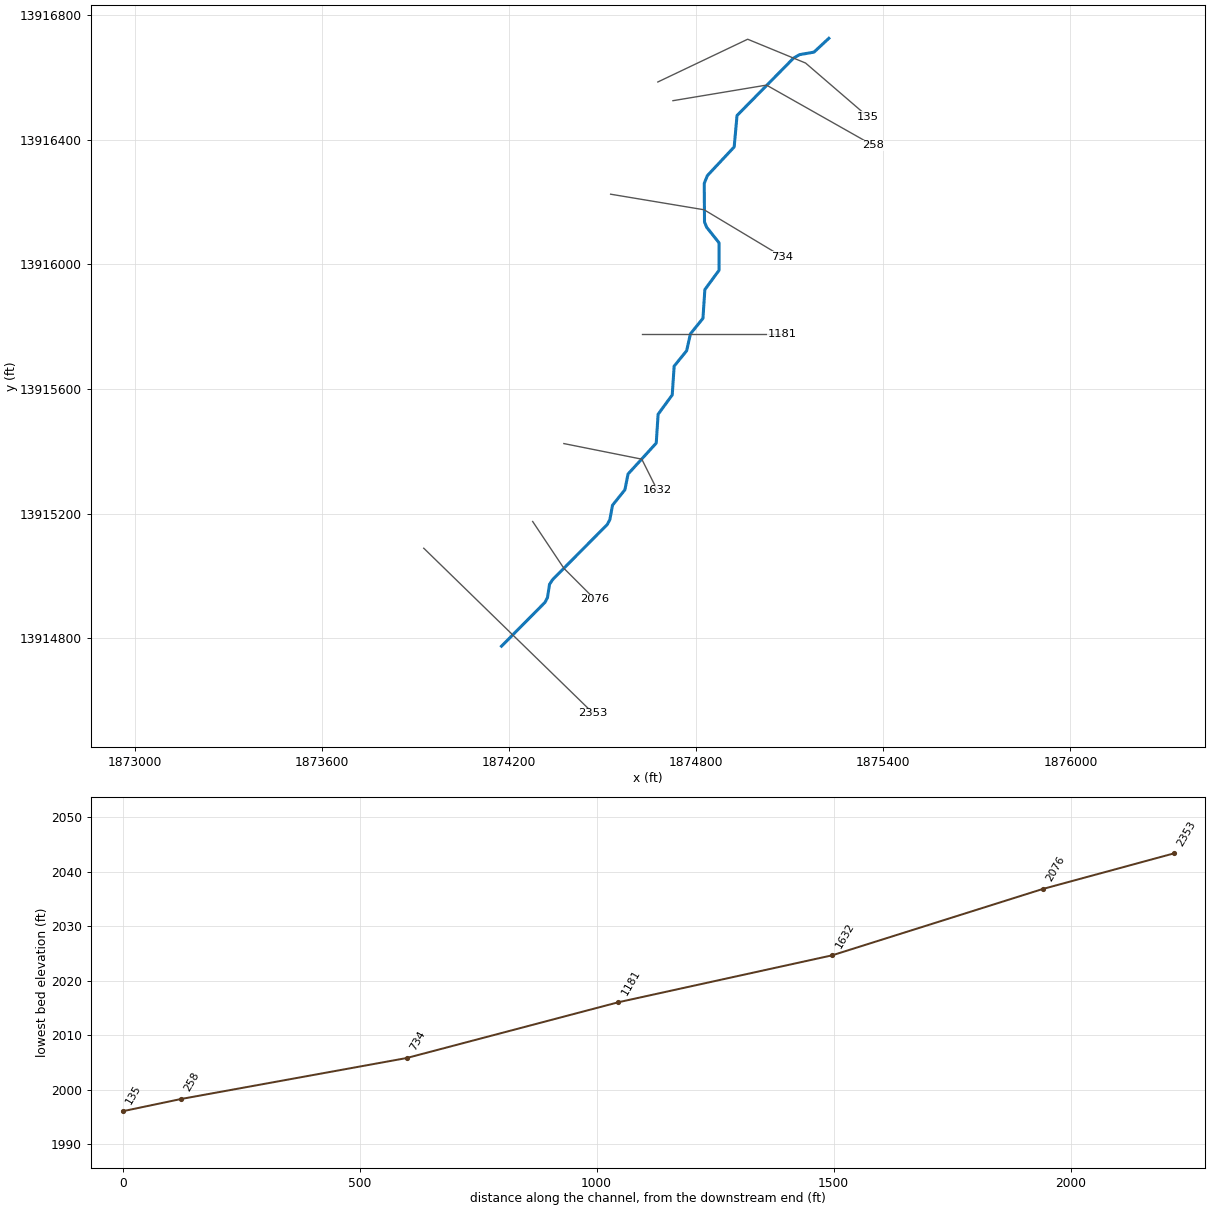
--- Stream0332.prj (project) ---

Proj Title=Stream0332 Base Level Engineering
Current Plan=p01
Default Exp/Contr=0.3,0.1
English Units
Geom File=g01
Flow File=f01
Plan File=p01
BEGIN DESCRIPTION:
Stream0332
END DESCRIPTION:

--- Stream0332.p01 (plan) ---

Plan Title=Multiple Run
Short Identifier=Multiple
Geom File=g01
Flow File=f01
Subcritical Flow
K Sum by GR= 0
Std Step Tol= 0.01
Critical Tol= 0.01
Num of Std Step Trials= 20
Max Error Tol= 0.3
Flow Tol Ratio= 0.001
Split Flow NTrial= 30
Split Flow Tol= 0.02
Split Flow Ratio= 0.02
Log Output Level= 0
Friction Slope Method= 1
Unsteady Friction Slope Method= 2
Unsteady Bridges Friction Slope Method= 1
Parabolic Critical Depth
Global Vel Dist=  1 , 1 , 1
Global Log Level= 0
CheckData=True
Encroach Param= -1, 0, 0, 0
BEGIN DESCRIPTION:
Multiple Run
END DESCRIPTION:

--- Stream0332.f01 (steady flow) ---

Flow Title=Multiple
Number of Profiles=7
Profile Names=10-year,25-year,50-year,1pct_min,100-year,1pct_plu,500-year
River Rch & RM= Stream0332,Reach-1,2353
     555     909    1235     814    1623    3239    2765
Boundary for River Rch & Prof#=Stream0332,Reach-1,1
Up Type=0
Dn Type=3
Dn Slope=0.005
Boundary for River Rch & Prof#=Stream0332,Reach-1,2
Up Type=0
Dn Type=3
Dn Slope=0.005
Boundary for River Rch & Prof#=Stream0332,Reach-1,3
Up Type=0
Dn Type=3
Dn Slope=0.005
Boundary for River Rch & Prof#=Stream0332,Reach-1,4
Up Type=0
Dn Type=3
Dn Slope=0.005
Boundary for River Rch & Prof#=Stream0332,Reach-1,5
Up Type=0
Dn Type=3
Dn Slope=0.005
Boundary for River Rch & Prof#=Stream0332,Reach-1,6
Up Type=0
Dn Type=3
Dn Slope=0.005
Boundary for River Rch & Prof#=Stream0332,Reach-1,7
Up Type=0
Dn Type=3
Dn Slope=0.005

--- Stream0332.g01 (geometry) ---

Geom Title=Existing Conditions

River Reach=Stream0332,Reach-1
Reach XY= 30
      1874175.00     13914775.00      1874314.23     13914915.32
      1874322.47     13914931.05      1874328.98     13914973.35
      1874338.63     13914988.21      1874514.24     13915165.32
      1874522.50     13915181.04      1874531.10     13915227.19
      1874570.81     13915276.73      1874580.85     13915327.29
      1874671.38     13915426.50      1874677.36     13915519.02
      1874722.65     13915580.97      1874728.83     13915673.42
      1874768.89     13915722.82      1874781.11     13915777.18
      1874821.17     13915826.58      1874827.36     13915919.03
      1874872.83     13915980.97      1874872.83     13916069.02
      1874833.14     13916118.94      1874826.21     13916135.51
      1874825.37     13916259.83      1874835.50     13916284.79
      1874921.37     13916376.50      1874930.52     13916477.43
      1875111.77     13916661.43      1875130.97     13916672.66
      1875177.35     13916680.71      1875225.00     13916725.00

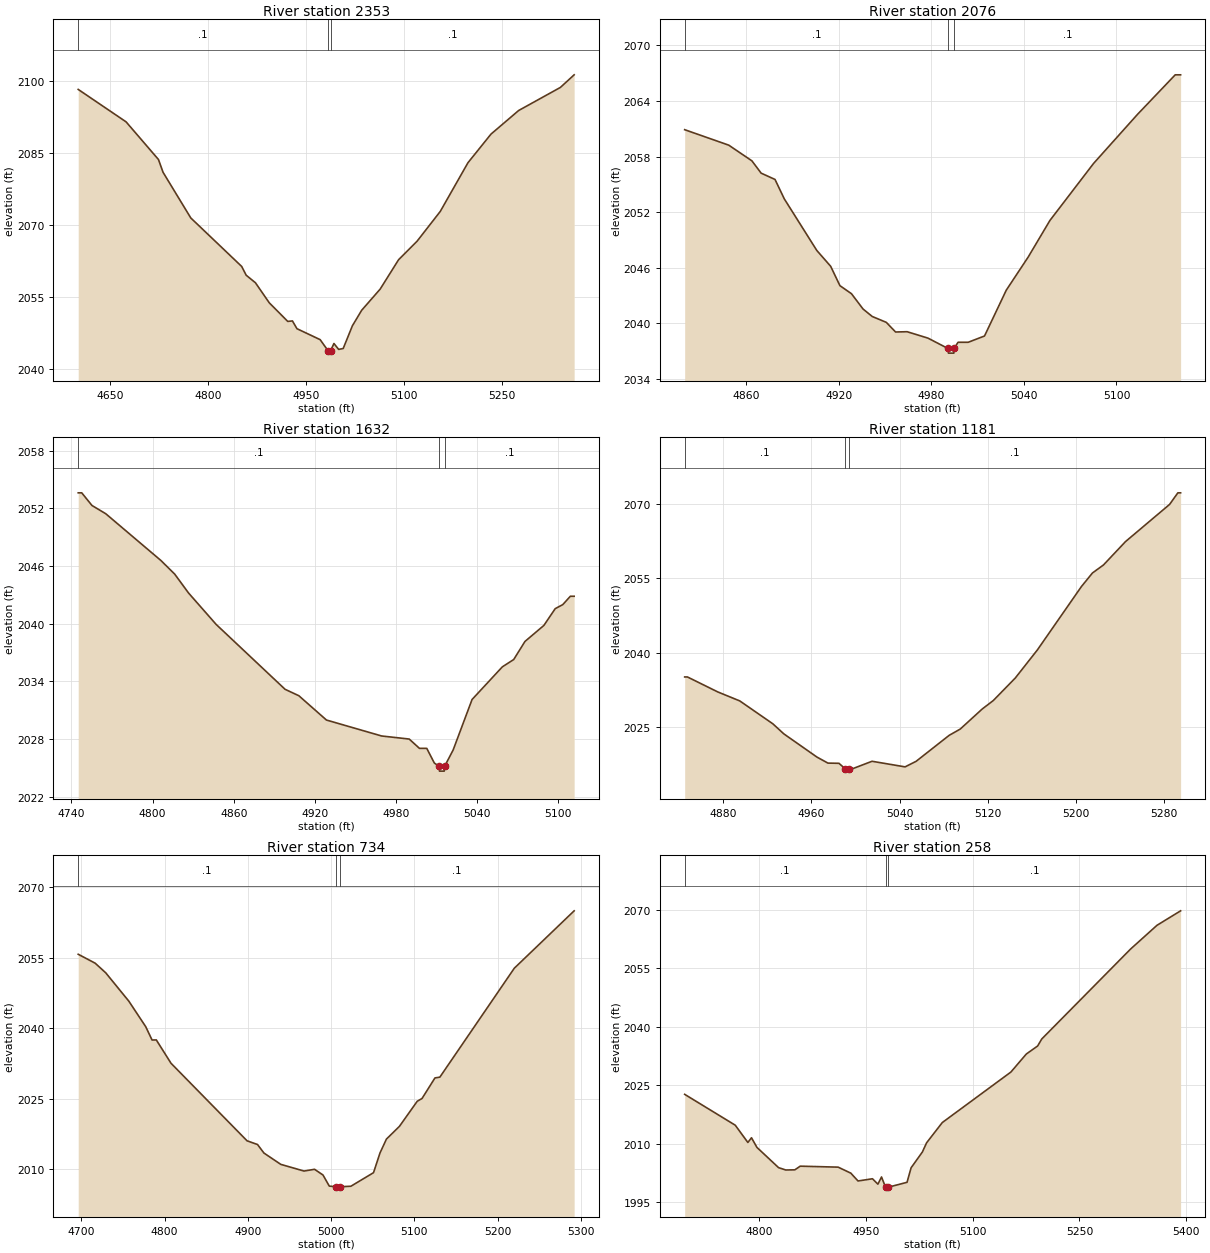
Type RM Length L Ch R = 1,2353,277,277,277
BEGIN DESCRIPTION:
Stream0332 9.0
END DESCRIPTION:
XS GIS Cut Line= 2
      1873925.54     13915089.30      1874469.44     13914559.48
#Sta/Elev= 30
  4601.3 2098.28  4674.6 2091.52  4724.2 2083.67  4731.2 2081.01  4773.7 2071.49
  4851.6 2061.39  4858.5 2059.56  4872.6 2058.00  4893.8 2053.82  4922.1 2049.94
  4929.3 2050.04  4936.2 2048.42  4971.7 2046.14  4983.8 2043.83  4984.1 2043.33
  4987.8 2043.83  4992.8 2045.34  5000.0 2044.11  5007.0 2044.29  5021.1 2049.03
  5035.3 2052.26  5063.6 2056.67  5091.8 2062.79  5120.1 2066.65  5155.6 2072.85
  5198.0 2083.00  5233.3 2088.97  5275.7 2093.89  5339.5 2098.69  5360.6 2101.32
#Mann=3,-1,0
  4601.3     0.1       0  4983.8    0.05       0  4987.8     0.1       0
Bank Sta=4983.8,4987.8
Exp/Cntr=0.3,0.1

Type RM Length L Ch R = 1,2076,444,444,444
BEGIN DESCRIPTION:
Stream0332 8.0
END DESCRIPTION:
XS GIS Cut Line= 3
      1874274.97     13915175.04      1874375.00     13915025.00
      1874474.97     13914925.03
#Sta/Elev= 30
  4819.9 2060.91  4848.5 2059.24  4863.5 2057.55  4869.5 2056.22  4878.5 2055.54
  4884.5 2053.45  4905.6 2047.88  4914.6 2046.17  4920.6 2044.08  4928.1 2043.21
  4935.6 2041.56  4941.6 2040.75  4950.7 2040.12  4956.7 2039.08  4964.2 2039.11
  4977.7 2038.42  4990.7 2037.30  4991.0 2036.80  4994.5 2036.80  4994.7 2037.30
  4997.2 2037.97  5003.8 2037.97  5014.4 2038.65  5028.5 2043.59  5042.7 2047.16
  5056.8 2051.11  5085.1 2057.26  5113.4 2062.52  5138.1 2066.83  5141.6 2066.83
#Mann=3,-1,0
  4819.9     0.1       0  4990.7    0.05       0  4994.7     0.1       0
Bank Sta=4990.7,4994.7
Exp/Cntr=0.3,0.1

Type RM Length L Ch R = 1,1632,451,451,451
BEGIN DESCRIPTION:
Stream0332 7.0
END DESCRIPTION:
XS GIS Cut Line= 3
      1874374.98     13915425.00      1874625.00     13915375.00
      1874675.01     13915274.98
#Sta/Elev= 30
  4745.0 2053.63  4747.6 2053.63  4755.2 2052.31  4765.4 2051.45  4806.2 2046.58
  4816.4 2045.16  4826.6 2043.20  4847.0 2039.93  4898.0 2033.17  4908.2 2032.50
  4928.6 2029.97  4969.4 2028.31  4989.8 2027.99  4997.4 2027.02  5002.8 2027.02
  5008.4 2025.49  5012.0 2025.15  5012.2 2024.65  5015.7 2024.65  5016.0 2025.15
  5022.3 2026.85  5036.3 2032.11  5058.7 2035.51  5067.1 2036.27  5075.4 2038.15
  5089.4 2039.82  5097.8 2041.57  5103.4 2041.99  5109.0 2042.86  5111.8 2042.86
#Mann=3,-1,0
  4745.0     0.1       0  5012.0    0.05       0  5016.0     0.1       0
Bank Sta=5012,5016
Exp/Cntr=0.3,0.1

Type RM Length L Ch R = 1,1181,447,447,447
BEGIN DESCRIPTION:
Stream0332 6.0
END DESCRIPTION:
XS GIS Cut Line= 3
      1874625.04     13915775.00      1874775.00     13915775.00
      1875075.04     13915775.00
#Sta/Elev= 30
  4845.0 2035.07  4847.5 2035.07  4875.0 2032.05  4895.0 2030.23  4925.0 2025.61
  4935.0 2023.57  4965.0 2018.89  4975.0 2017.67  4985.0 2017.63  4990.5 2016.55
  4990.7 2016.05  4994.2 2016.05  4994.5 2016.55  4997.5 2016.55  5015.0 2018.04
  5045.0 2016.91  5055.0 2018.03  5085.0 2023.28  5095.0 2024.54  5115.0 2028.60
  5125.0 2030.30  5145.0 2034.86  5165.0 2040.52  5205.0 2053.33  5215.0 2056.07
  5225.0 2057.69  5245.0 2062.41  5285.0 2069.92  5292.5 2072.26  5295.0 2072.26
#Mann=3,-1,0
  4845.0     0.1       0  4990.5    0.05       0  4994.5     0.1       0
Bank Sta=4990.5,4994.5
Exp/Cntr=0.3,0.1

Type RM Length L Ch R = 1,734,476,476,476
BEGIN DESCRIPTION:
Stream0332 5.0
END DESCRIPTION:
XS GIS Cut Line= 3
      1874524.98     13916225.00      1874825.00     13916175.00
      1875075.00     13916025.00
#Sta/Elev= 30
  4696.3 2055.69  4716.6 2053.80  4729.3 2051.76  4757.1 2045.73  4777.4 2040.31
  4785.0 2037.48  4790.1 2037.50  4807.8 2032.54  4899.1 2016.08  4911.7 2015.29
  4919.4 2013.48  4939.6 2011.08  4967.5 2009.66  4980.2 2010.03  4990.3 2008.82
  4997.9 2006.46  5006.2 2006.32  5006.5 2005.82  5010.2 2006.32  5023.8 2006.43
  5051.0 2009.31  5058.8 2013.50  5066.5 2016.44  5082.1 2019.14  5103.5 2024.47
  5109.3 2025.07  5124.8 2029.43  5130.7 2029.60  5220.1 2052.72  5292.0 2064.91
#Mann=3,-1,0
  4696.3     0.1       0  5006.2    0.05       0  5010.2     0.1       0
Bank Sta=5006.2,5010.2
Exp/Cntr=0.3,0.1

Type RM Length L Ch R = 1,258,123,123,123
BEGIN DESCRIPTION:
Stream0332 4.0
END DESCRIPTION:
XS GIS Cut Line= 3
      1874724.99     13916525.00      1875025.00     13916575.00
      1875366.18     13916382.08
#Sta/Elev= 30
  4695.9 2022.63  4766.9 2014.71  4784.6 2010.28  4789.7 2011.49  4797.3 2009.02
  4827.7 2003.82  4837.8 2003.22  4850.5 2003.26  4858.1 2004.20  4911.3 2003.95
  4929.1 2002.41  4939.2 2000.40  4959.5 2000.97  4967.1 1999.58  4972.2 2001.43
  4977.8 1998.81  4978.0 1998.31  4981.8 1998.81  5008.0 2000.06  5013.7 2003.78
  5029.6 2007.85  5035.4 2010.18  5057.5 2015.39  5153.8 2028.35  5175.4 2032.97
  5191.3 2035.03  5197.1 2036.83  5321.7 2059.89  5358.8 2065.99  5392.0 2069.71
#Mann=3,-1,0
  4695.9     0.1       0  4977.8    0.05       0  4981.8     0.1       0
Bank Sta=4977.8,4981.8
Exp/Cntr=0.3,0.1

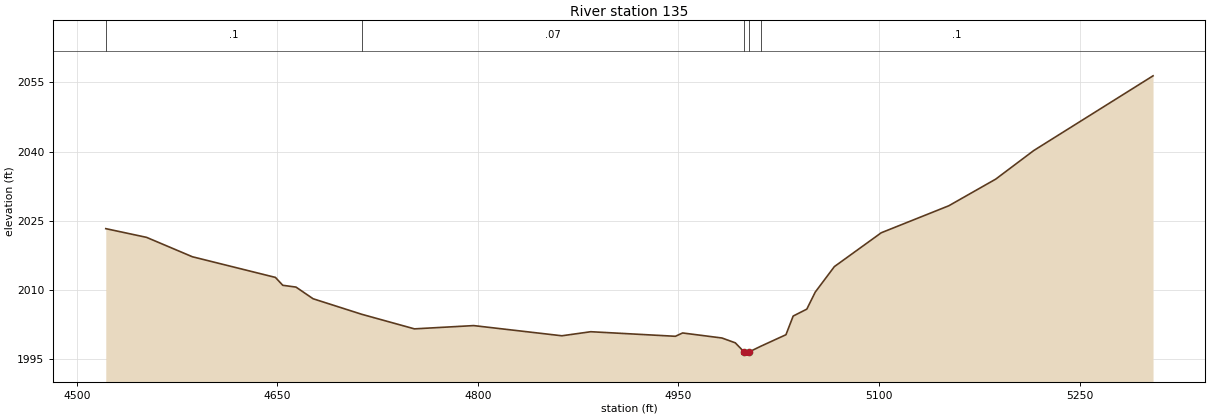
Type RM Length L Ch R = 1,135,0,0,0
BEGIN DESCRIPTION:
Stream0332 T
END DESCRIPTION:
XS GIS Cut Line= 4
      1874676.47     13916584.99      1874964.65     13916722.13
      1875150.41     13916645.74      1875350.03     13916473.90
#Sta/Elev= 30
  4521.6 2023.29  4552.1 2021.40  4586.4 2017.19  4648.5 2012.71  4654.0 2011.00
  4663.9 2010.61  4676.7 2008.08  4713.1 2004.71  4752.5 2001.55  4796.8 2002.26
  4862.8 2000.05  4884.4 2000.93  4947.7 1999.94  4953.1 2000.66  4982.5 1999.57
  4992.5 1998.52  4999.0 1996.57  4999.3 1996.07  5003.0 1996.57  5011.5 1997.77
  5030.4 2000.28  5035.8 2004.33  5046.0 2005.83  5052.3 2009.52  5066.6 2015.05
  5101.7 2022.40  5152.2 2028.25  5187.3 2034.03  5215.8 2040.24  5305.0 2056.44
#Mann=5,-1,0
  4521.6     0.1       0  4713.1    0.07       0  4999.0    0.05       0
  5003.0    0.07       0  5011.5     0.1       0
Bank Sta=4999,5003
Exp/Cntr=0.3,0.1

Chan Stop Cuts=-1