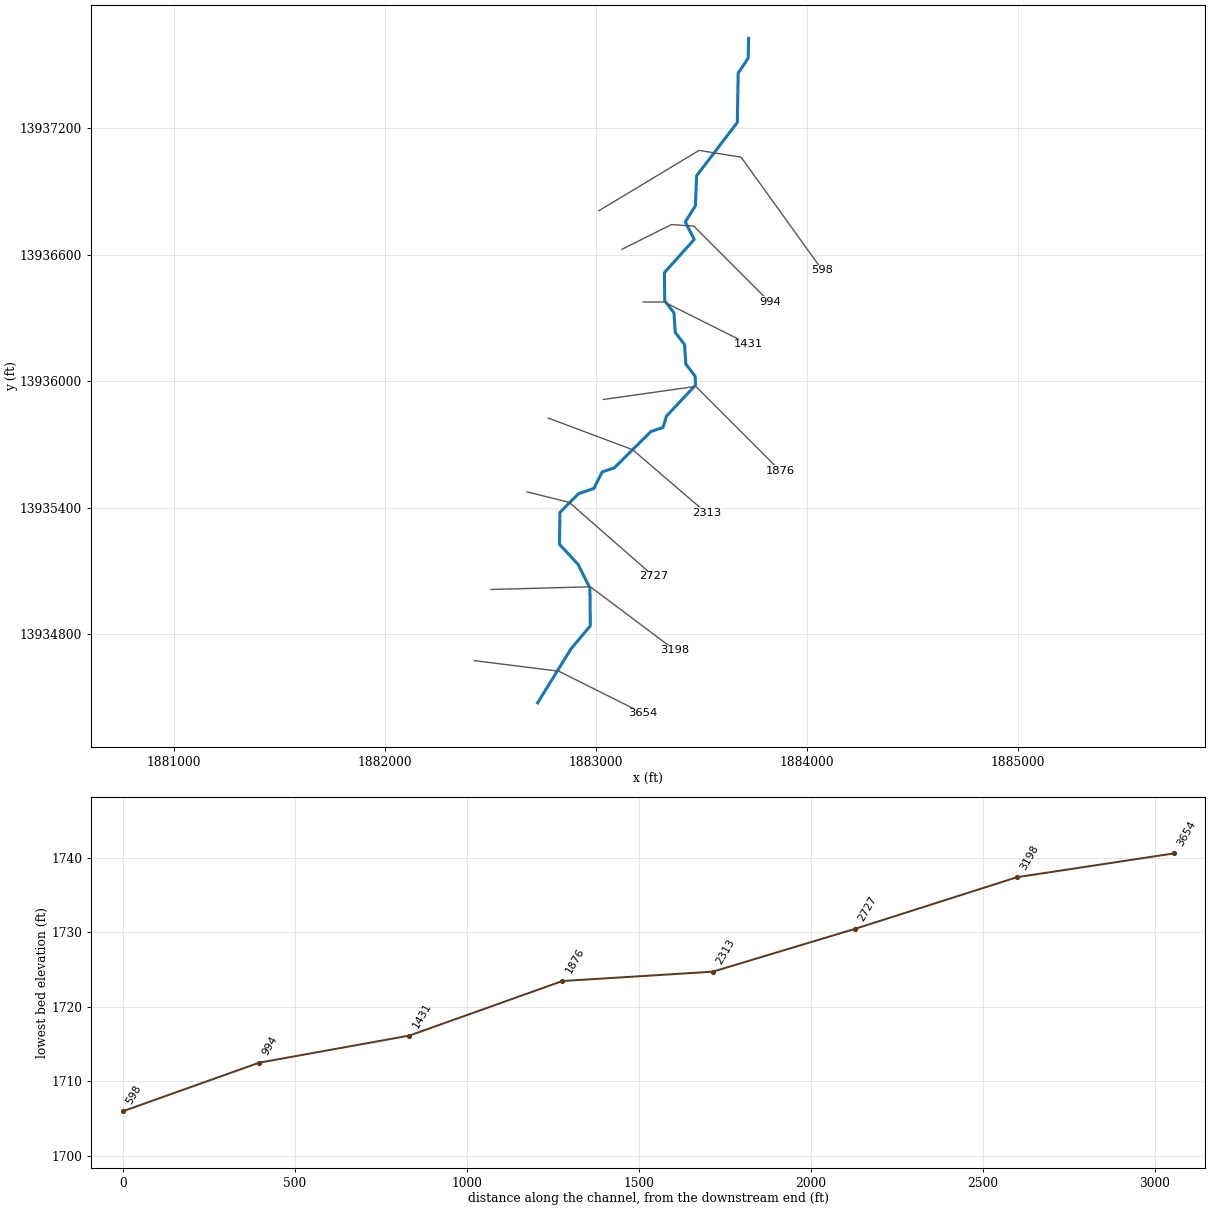
--- Stream0335.prj (project) ---

Proj Title=Stream0335 Base Level Engineering
Current Plan=p01
Default Exp/Contr=0.3,0.1
English Units
Geom File=g01
Flow File=f01
Plan File=p01
BEGIN DESCRIPTION:
Stream0335
END DESCRIPTION:

--- Stream0335.p01 (plan) ---

Plan Title=Multiple Run
Short Identifier=Multiple
Geom File=g01
Flow File=f01
Subcritical Flow
K Sum by GR= 0
Std Step Tol= 0.01
Critical Tol= 0.01
Num of Std Step Trials= 20
Max Error Tol= 0.3
Flow Tol Ratio= 0.001
Split Flow NTrial= 30
Split Flow Tol= 0.02
Split Flow Ratio= 0.02
Log Output Level= 0
Friction Slope Method= 1
Unsteady Friction Slope Method= 2
Unsteady Bridges Friction Slope Method= 1
Parabolic Critical Depth
Global Vel Dist=  1 , 1 , 1
Global Log Level= 0
CheckData=True
Encroach Param= -1, 0, 0, 0
BEGIN DESCRIPTION:
Multiple Run
END DESCRIPTION:

--- Stream0335.f01 (steady flow) ---

Flow Title=Multiple
Number of Profiles=7
Profile Names=10-year,25-year,50-year,1pct_min,100-year,1pct_plu,500-year
River Rch & RM= Stream0335,Reach-1,3654
    1738    3068    4377    3016    6018   12007   11245
Boundary for River Rch & Prof#=Stream0335,Reach-1,1
Up Type=0
Dn Type=3
Dn Slope=0.005
Boundary for River Rch & Prof#=Stream0335,Reach-1,2
Up Type=0
Dn Type=3
Dn Slope=0.005
Boundary for River Rch & Prof#=Stream0335,Reach-1,3
Up Type=0
Dn Type=3
Dn Slope=0.005
Boundary for River Rch & Prof#=Stream0335,Reach-1,4
Up Type=0
Dn Type=3
Dn Slope=0.005
Boundary for River Rch & Prof#=Stream0335,Reach-1,5
Up Type=0
Dn Type=3
Dn Slope=0.005
Boundary for River Rch & Prof#=Stream0335,Reach-1,6
Up Type=0
Dn Type=3
Dn Slope=0.005
Boundary for River Rch & Prof#=Stream0335,Reach-1,7
Up Type=0
Dn Type=3
Dn Slope=0.005

--- Stream0335.g01 (geometry) ---

Geom Title=Existing Conditions

River Reach=Stream0335,Reach-1
Reach XY= 30
      1882725.00     13934475.00      1882883.18     13934731.04
      1882974.62     13934840.16      1882972.76     13935019.07
      1882916.84     13935131.05      1882828.54     13935226.47
      1882830.45     13935377.46      1882918.95     13935466.84
      1882992.01     13935491.58      1883030.63     13935569.35
      1883087.98     13935588.72      1883262.02     13935761.27
      1883319.38     13935780.62      1883335.89     13935834.42
      1883473.38     13935981.03      1883471.66     13936023.25
      1883427.38     13936080.97      1883421.15     13936173.40
      1883377.35     13936230.97      1883371.14     13936323.40
      1883327.25     13936380.94      1883326.04     13936514.56
      1883467.18     13936671.59      1883424.79     13936754.79
      1883472.70     13936830.93      1883478.55     13936973.53
      1883671.45     13937226.47      1883675.51     13937459.79
      1883722.90     13937530.87      1883725.00     13937625.00

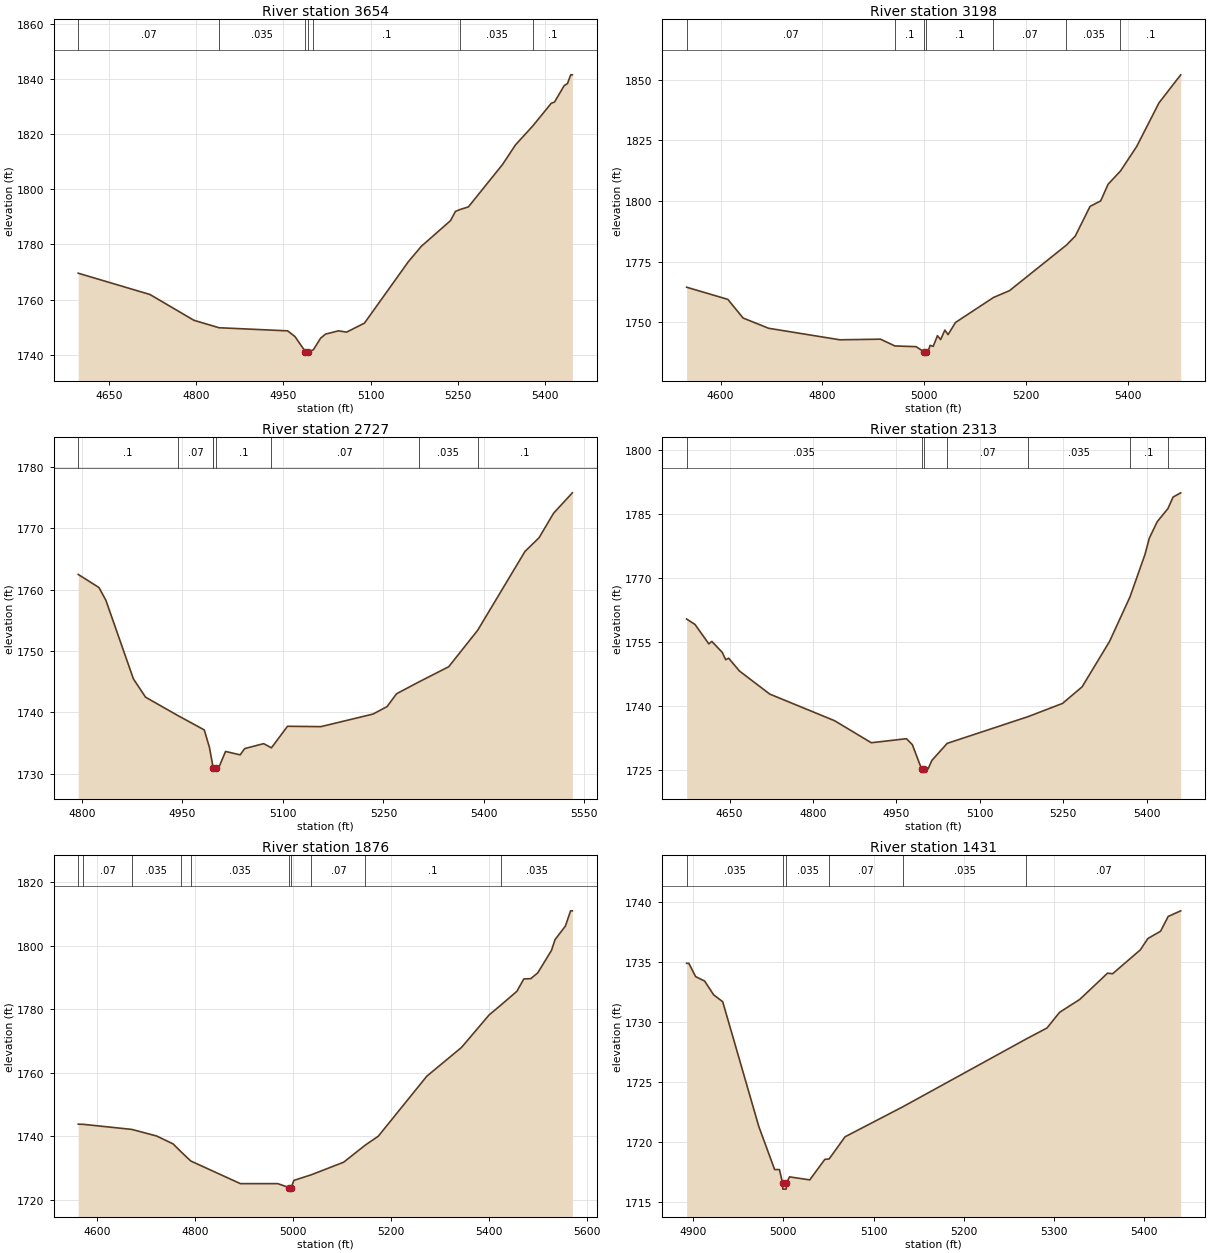
Type RM Length L Ch R = 1,3654,456,456,456
BEGIN DESCRIPTION:
Stream0335 8.0
END DESCRIPTION:
XS GIS Cut Line= 3
      1882425.01     13934675.00      1882825.00     13934625.00
      1883224.99     13934425.01
#Sta/Elev= 30
  4596.9 1769.54  4720.3 1761.82  4795.9 1752.47  4839.2 1749.76  4957.2 1748.63
  4969.8 1746.58  4987.9 1741.05  4988.2 1740.55  4992.0 1741.05  5001.5 1741.76
  5014.0 1745.97  5022.4 1747.45  5044.7 1748.63  5058.7 1748.17  5089.4 1751.43
  5164.9 1773.70  5187.3 1779.30  5237.6 1788.63  5246.0 1791.97  5254.4 1792.68
  5268.3 1793.60  5327.0 1808.97  5349.4 1816.11  5379.2 1822.99  5410.9 1831.19
  5416.5 1831.64  5433.2 1837.61  5438.8 1838.33  5444.4 1841.51  5447.2 1841.51
#Mann=7,-1,0
  4596.9    0.07       0  4839.2   0.035       0  4987.9   0.035       0
  4992.0   0.035       0  5001.5     0.1       0  5254.4   0.035       0
  5379.2     0.1       0
Bank Sta=4987.9,4992
Exp/Cntr=0.3,0.1

Type RM Length L Ch R = 1,3198,471,471,471
BEGIN DESCRIPTION:
Stream0335 7.0
END DESCRIPTION:
XS GIS Cut Line= 3
      1882503.90     13935012.29      1882975.00     13935025.00
      1883375.02     13934724.98
#Sta/Elev= 30
  4533.2 1764.51  4614.3 1759.50  4644.3 1751.82  4694.4 1747.60  4834.4 1742.85
  4914.4 1743.11  4942.6 1740.32  4984.5 1740.02  4999.9 1737.86  5000.2 1737.36
  5004.0 1737.86  5007.6 1737.86  5011.8 1740.56  5018.0 1740.16  5026.3 1744.55
  5032.6 1742.94  5040.9 1746.85  5047.2 1744.98  5061.8 1749.99  5136.4 1760.27
  5168.0 1763.10  5279.9 1781.88  5297.2 1785.56  5326.3 1797.80  5347.2 1800.07
  5361.8 1806.93  5386.0 1812.35  5418.0 1822.48  5461.8 1840.44  5504.5 1851.99
#Mann=7,-1,0
  4533.2    0.07       0  4942.6     0.1       0  4999.9    0.05       0
  5004.0     0.1       0  5136.4    0.07       0  5279.9   0.035       0
  5386.0     0.1       0
Bank Sta=4999.9,5004
Exp/Cntr=0.3,0.1

Type RM Length L Ch R = 1,2727,414,414,414
BEGIN DESCRIPTION:
Stream0335 6.0
END DESCRIPTION:
XS GIS Cut Line= 3
      1882675.02     13935475.00      1882875.00     13935425.00
      1883274.97     13935075.03
#Sta/Elev= 30
  4794.4 1762.48  4825.3 1760.35  4835.6 1758.29  4876.8 1745.45  4894.9 1742.48
  4943.2 1739.48  4982.5 1737.15  4990.2 1734.33  4995.7 1731.05  4995.9 1730.93
  4996.2 1730.43  5000.1 1730.93  5003.9 1730.93  5014.3 1733.64  5036.1 1733.08
  5042.8 1734.10  5071.2 1734.91  5082.8 1734.23  5106.8 1737.74  5156.7 1737.68
  5234.5 1739.73  5255.4 1740.95  5269.6 1743.04  5302.8 1744.96  5347.4 1747.44
  5390.7 1753.39  5461.3 1766.23  5482.2 1768.45  5504.0 1772.46  5532.0 1775.78
#Mann=8,-1,0
  4794.4     0.1       0  4943.2    0.07       0  4995.7     0.1       0
  4995.9    0.05       0  5000.1     0.1       0  5082.8    0.07       0
  5302.8   0.035       0  5390.7     0.1       0
Bank Sta=4995.9,5000.1
Exp/Cntr=0.3,0.1

Type RM Length L Ch R = 1,2313,437,437,437
BEGIN DESCRIPTION:
Stream0335 5.0
END DESCRIPTION:
XS GIS Cut Line= 3
      1882775.01     13935825.00      1883175.00     13935675.00
      1883525.02     13935374.98
#Sta/Elev= 30
  4572.8 1760.32  4587.9 1759.05  4612.8 1754.50  4618.2 1755.07  4636.9 1752.51
  4643.1 1750.78  4648.4 1751.14  4668.0 1748.12  4722.3 1742.73  4838.9 1736.49
  4904.8 1731.33  4968.0 1732.28  4978.6 1730.88  4995.2 1725.18  4995.5 1724.68
  4999.4 1725.18  5007.1 1725.25  5013.7 1727.19  5041.2 1731.18  5186.9 1737.46
  5248.6 1740.55  5283.7 1744.42  5333.1 1755.07  5369.8 1765.50  5396.8 1775.46
  5404.4 1779.21  5418.7 1783.11  5438.0 1786.19  5447.3 1788.90  5461.0 1789.89
#Mann=7,-1,0
  4572.8   0.035       0  4995.2   0.035       0  4999.4   0.035       0
  5041.2    0.07       0  5186.9   0.035       0  5369.8     0.1       0
  5438.0   0.035       0
Bank Sta=4995.2,4999.4
Exp/Cntr=0.3,0.1

Type RM Length L Ch R = 1,1876,445,445,445
BEGIN DESCRIPTION:
Stream0335 4.0
END DESCRIPTION:
XS GIS Cut Line= 3
      1883036.86     13935913.14      1883475.00     13935975.00
      1883875.02     13935574.98
#Sta/Elev= 30
  4561.8 1743.85  4572.1 1743.80  4671.2 1742.20  4721.5 1740.14  4755.4 1737.64
  4771.4 1735.19  4791.3 1732.28  4892.6 1725.16  4968.7 1725.16  4992.0 1723.93
  4992.3 1723.43  4996.3 1723.93  5001.8 1726.18  5037.5 1727.95  5103.3 1731.89
  5147.7 1737.29  5174.0 1740.06  5273.0 1758.93  5343.7 1767.95  5400.3 1778.21
  5423.6 1781.21  5456.8 1785.61  5471.0 1789.51  5485.1 1789.59  5499.3 1791.39
  5527.5 1798.50  5534.6 1801.84  5555.8 1806.12  5566.4 1810.91  5570.0 1810.91
#Mann=10,-1,0
  4561.8   0.035       0  4572.1    0.07       0  4671.2   0.035       0
  4771.4    0.07       0  4791.3   0.035       0  4992.0   0.035       0
  4996.3   0.035       0  5037.5    0.07       0  5147.7     0.1       0
  5423.6   0.035       0
Bank Sta=4992,4996.3
Exp/Cntr=0.3,0.1

Type RM Length L Ch R = 1,1431,437,437,437
BEGIN DESCRIPTION:
Stream0335 3.0
END DESCRIPTION:
XS GIS Cut Line= 3
      1883224.98     13936375.00      1883325.00     13936375.00
      1883724.97     13936175.01
#Sta/Elev= 30
  4893.0 1734.92  4895.5 1734.92  4903.0 1733.81  4913.0 1733.44  4923.0 1732.29
  4933.0 1731.72  4973.0 1721.32  4990.5 1717.74  4995.8 1717.74  4999.3 1716.61
  4999.6 1716.11  5003.3 1716.11  5003.6 1716.61  5007.0 1717.13  5029.4 1716.88
  5046.1 1718.59  5050.8 1718.62  5068.5 1720.47  5132.5 1722.97  5269.2 1728.62
  5292.1 1729.53  5306.1 1730.84  5328.4 1731.91  5359.2 1734.10  5364.8 1734.05
  5395.5 1736.04  5403.9 1736.99  5417.9 1737.59  5426.3 1738.82  5440.2 1739.29
#Mann=6,-1,0
  4893.0   0.035       0  4999.3   0.035       0  5003.6   0.035       0
  5050.8    0.07       0  5132.5   0.035       0  5269.2    0.07       0
Bank Sta=4999.3,5003.6
Exp/Cntr=0.3,0.1

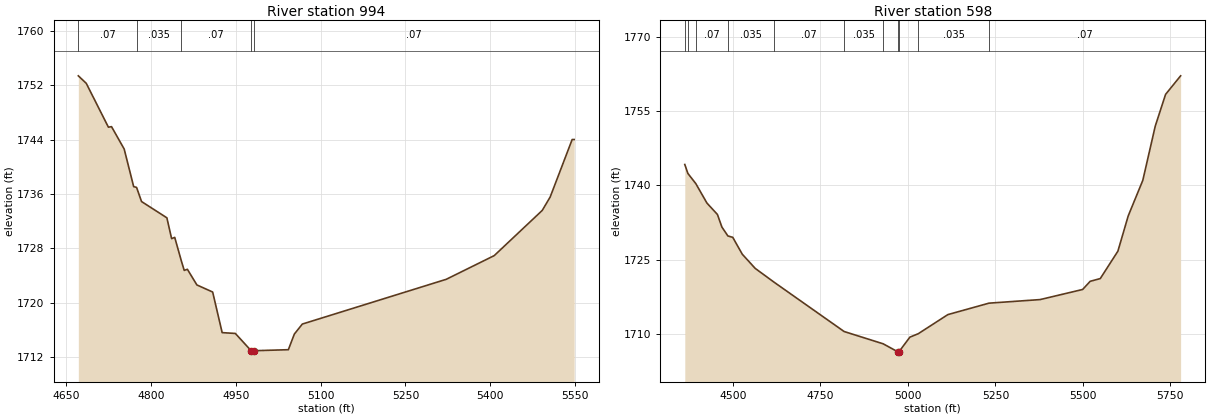
Type RM Length L Ch R = 1,994,396,396,396
BEGIN DESCRIPTION:
Stream0335 2.0
END DESCRIPTION:
XS GIS Cut Line= 4
      1883124.96     13936624.98      1883359.33     13936742.17
      1883465.07     13936734.93      1883824.97     13936375.03
#Sta/Elev= 30
  4671.5 1753.38  4685.5 1752.28  4724.7 1745.83  4730.2 1745.91  4752.6 1742.62
  4769.4 1737.09  4774.5 1736.98  4783.3 1734.90  4828.1 1732.51  4836.5 1729.45
  4842.0 1729.63  4853.9 1726.12  4858.8 1724.78  4864.4 1724.94  4881.2 1722.64
  4909.1 1721.60  4925.9 1715.63  4949.2 1715.51  4977.2 1712.97  4977.4 1712.47
  4981.5 1712.97  5043.0 1713.12  5053.6 1715.42  5067.7 1716.89  5322.3 1723.47
  5407.1 1726.95  5492.0 1733.59  5506.1 1735.57  5545.0 1744.02  5548.5 1744.02
#Mann=5,-1,0
  4671.5    0.07       0  4774.5   0.035       0  4853.9    0.07       0
  4977.2    0.05       0  4981.5    0.07       0
Bank Sta=4977.2,4981.5
Exp/Cntr=0.3,0.1

Type RM Length L Ch R = 1,598,0,0,0
BEGIN DESCRIPTION:
Stream0335 1.0
END DESCRIPTION:
XS GIS Cut Line= 4
      1883015.10     13936807.77      1883490.34     13937093.96
      1883689.85     13937061.23      1884075.03     13936524.96
#Sta/Elev= 30
  4362.2 1744.20  4371.0 1742.40  4393.7 1740.34  4425.5 1736.42  4455.5 1734.12
  4468.2 1731.59  4485.4 1729.79  4499.3 1729.51  4526.5 1726.11  4563.4 1723.25
  4617.1 1720.48  4817.6 1710.52  4929.2 1708.04  4970.2 1706.46  4970.5 1705.96
  4974.6 1706.46  5005.5 1709.38  5029.6 1710.08  5114.1 1713.93  5231.8 1716.24
  5377.9 1716.96  5499.4 1719.00  5520.8 1720.64  5549.8 1721.20  5600.1 1726.72
  5629.6 1733.83  5671.3 1741.00  5706.9 1751.94  5736.4 1758.34  5779.4 1762.08
#Mann=11,-1,0
  4362.2    0.07       0  4371.0     0.1       0  4393.7    0.07       0
  4485.4   0.035       0  4617.1    0.07       0  4817.6   0.035       0
  4929.2    0.07       0  4970.2    0.05       0  4974.6    0.07       0
  5029.6   0.035       0  5231.8    0.07       0
Bank Sta=4970.2,4974.6
Exp/Cntr=0.3,0.1

Chan Stop Cuts=-1