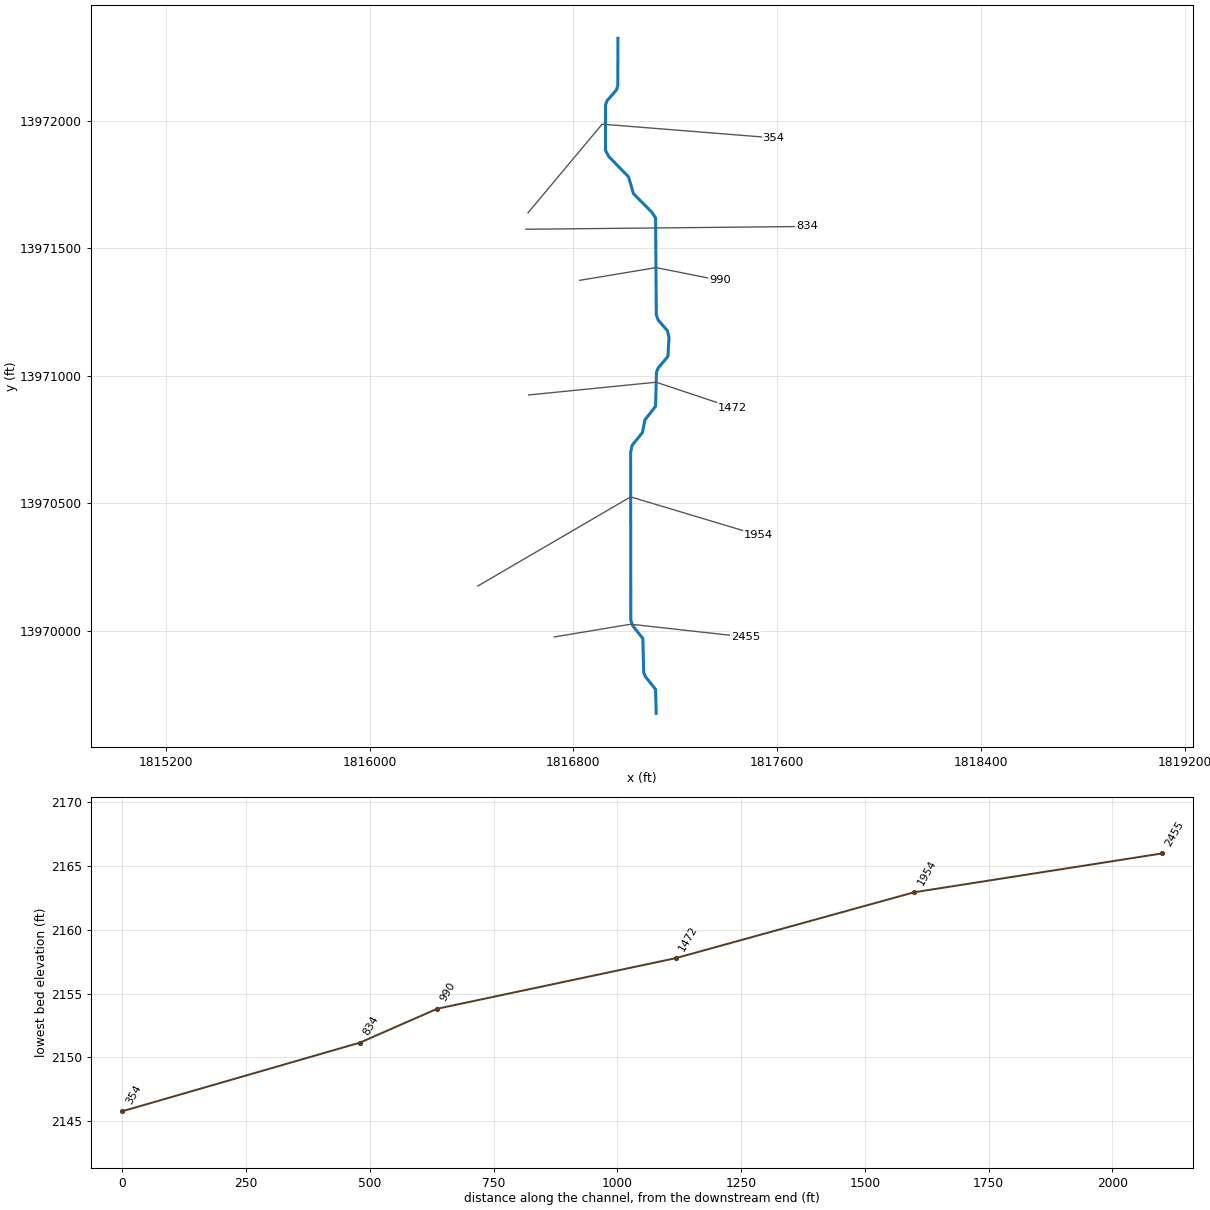
--- Stream0337.prj (project) ---

Proj Title=Stream0337 Base Level Engineering
Current Plan=p01
Default Exp/Contr=0.3,0.1
English Units
Geom File=g01
Flow File=f01
Plan File=p01
Y Axis Title=Elevation
X Axis Title(PF)=Main Channel Distance
X Axis Title(XS)=Station
BEGIN DESCRIPTION:
Stream0337
END DESCRIPTION:
DSS Export Rating Curves= 0
DSS Export Rating Curve Sorted= 0
DSS Export Volume Flow Curves= 0
DXF OffsetX= 0
DXF OffsetY= 0
DXF ScaleX= 1
DXF ScaleY= 10

--- Stream0337.p01 (plan) ---

Plan Title=Multiple Run
Short Identifier=Multiple
Geom File=g01
Flow File=f01
Subcritical Flow
K Sum by GR= 0
Std Step Tol= 0.01
Critical Tol= 0.01
Num of Std Step Trials= 20
Max Error Tol= 0.3
Flow Tol Ratio= 0.001
Split Flow NTrial= 30
Split Flow Tol= 0.02
Split Flow Ratio= 0.02
Log Output Level= 0
Friction Slope Method= 1
Unsteady Friction Slope Method= 2
Unsteady Bridges Friction Slope Method= 1
Parabolic Critical Depth
Global Vel Dist=  1 , 1 , 1
Global Log Level= 0
CheckData=True
Encroach Param= -1, 0, 0, 0
BEGIN DESCRIPTION:
Multiple Run
END DESCRIPTION:

--- Stream0337.f01 (steady flow) ---

Flow Title=Multiple
Program Version=4.10
Number of Profiles= 7
Profile Names=10-year,25-year,50-year,1pct_min,100-year,1pct_plu,500-year
River Rch & RM=Stream0337,Reach-1         ,2455
    1007    1697    2344    1563    3118    6221    5456
Boundary for River Rch & Prof#=Stream0337,Reach-1         , 1
Up Type= 0
Dn Type= 3
Dn Slope=0.01
Boundary for River Rch & Prof#=Stream0337,Reach-1         , 2
Up Type= 0
Dn Type= 3
Dn Slope=0.01
Boundary for River Rch & Prof#=Stream0337,Reach-1         , 3
Up Type= 0
Dn Type= 3
Dn Slope=0.01
Boundary for River Rch & Prof#=Stream0337,Reach-1         , 4
Up Type= 0
Dn Type= 3
Dn Slope=0.01
Boundary for River Rch & Prof#=Stream0337,Reach-1         , 5
Up Type= 0
Dn Type= 3
Dn Slope=0.01
Boundary for River Rch & Prof#=Stream0337,Reach-1         , 6
Up Type= 0
Dn Type= 3
Dn Slope=0.01
Boundary for River Rch & Prof#=Stream0337,Reach-1         , 7
Up Type= 0
Dn Type= 3
Dn Slope=0.01
DSS Import GetInterval= 0
DSS Import GetPeak= 0
DSS Import FillOption= 0

--- Stream0337.g01 (geometry) ---

Geom Title=Existing Conditions
Program Version=4.10

River Reach=Stream0337      ,Reach-1
Reach XY= 30
        1817125.       13969675.       1817122.9     13969769.13
       1817083.1     13969818.93      1817076.21      13969835.5
      1817072.73     13969969.06      1817033.14     13970018.94
      1817025.52     13970040.22      1817024.79     13970700.09
      1817030.71     13970727.35      1817070.81     13970776.74
      1817081.12     13970827.18      1817122.75     13970880.93
      1817126.23     13971014.49      1817133.15     13971031.06
       1817171.3      13971076.6       1817175.4       13971150.
      1817169.32     13971177.31      1817133.15     13971218.94
      1817125.52     13971240.22      1817122.94     13971619.14
      1817108.54     13971641.75       1817035.8     13971715.33
      1817016.82     13971781.04       1816938.4     13971861.69
      1816926.05     13971885.44      1816926.22     13972064.49
      1816933.14     13972081.06      1816969.26     13972122.66
      1816974.49     13972140.21        1816975.       13972325.

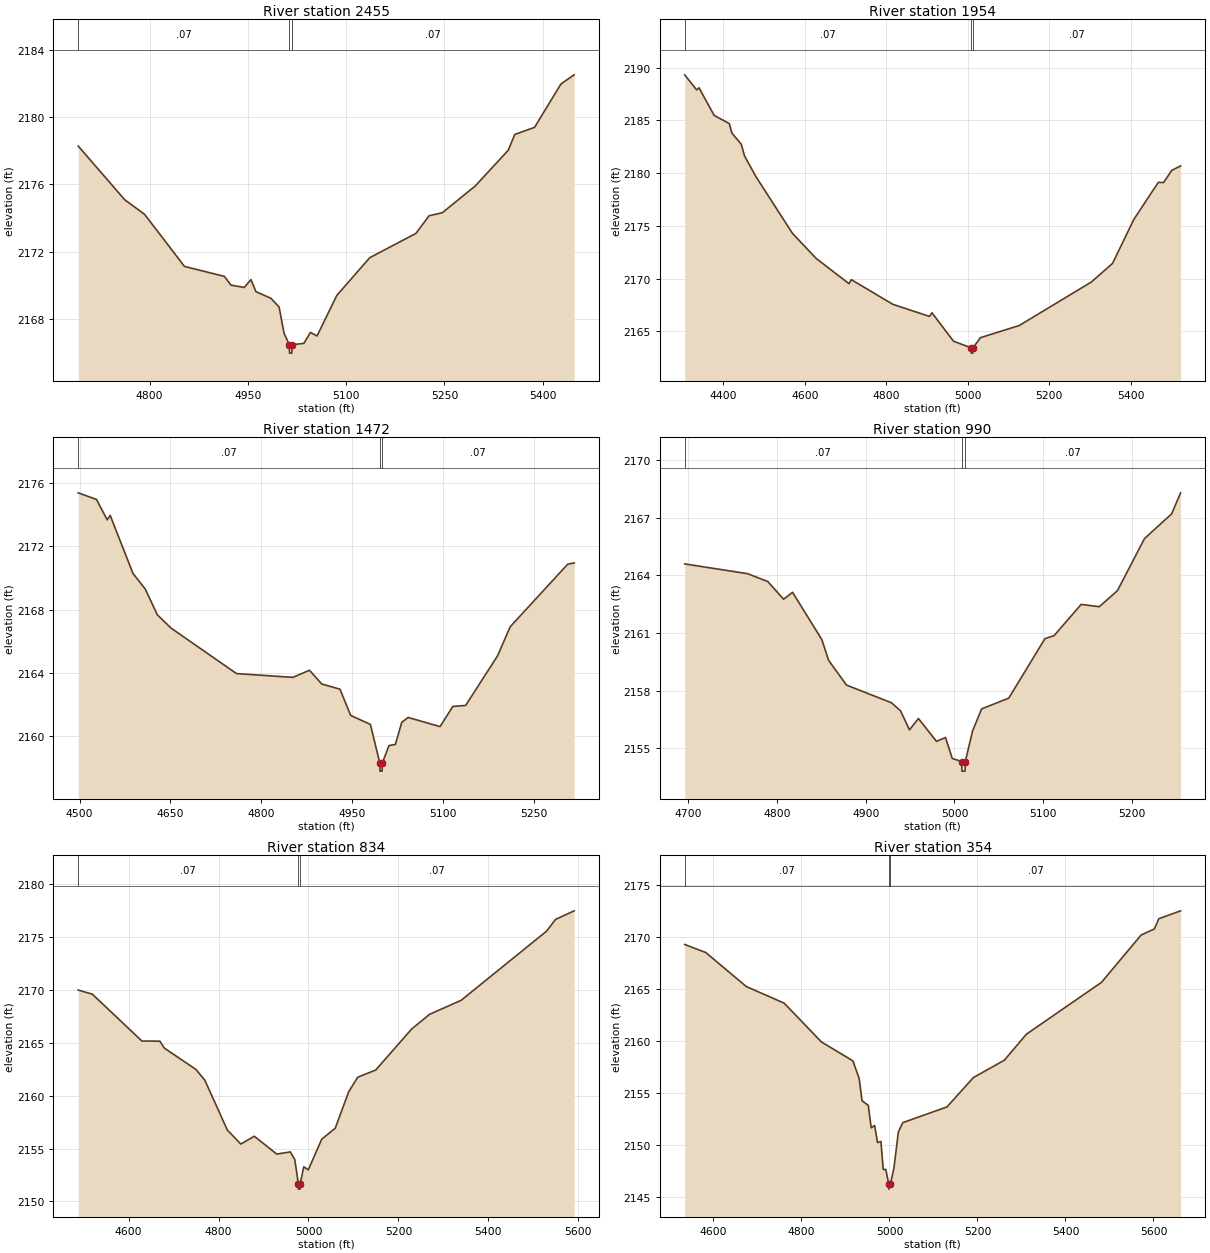
Type RM Length L Ch R = 1 ,2455    ,501,501,501
BEGIN DESCRIPTION:
Stream0337 5.0
END DESCRIPTION:
XS GIS Cut Line= 3
      1816725.01       13969975.        1817025.       13970025.
        1817475.       13969975.
#Sta/Elev= 30
    4691 2178.27    4762 2175.08  4792.4 2174.21  4853.2 2171.12    4914 2170.53
  4924.2 2170.01  4944.4 2169.87  4954.6 2170.34  4962.2 2169.62    4985 2169.23
  4997.6 2168.71  5005.2 2167.14  5013.3 2166.47  5013.5 2165.97    5017 2165.97
  5017.3 2166.47  5035.4 2166.55  5045.4  2167.2  5055.5 2166.99  5085.7  2169.4
    5136 2171.64  5206.4 2173.08  5226.5 2174.13  5246.7 2174.31    5297  2175.9
  5347.3 2178.02  5357.3 2178.96  5387.5 2179.38  5427.8 2181.96  5447.9  2182.5
#Mann= 3 ,-1 , 0
    4691     .07       0  5013.3     .05       0  5017.3     .07       0
Bank Sta=5013.3,5017.3
XS Rating Curve= 0 ,0
Exp/Cntr=0.3,0.1

Type RM Length L Ch R = 1 ,1954    ,482,482,482
BEGIN DESCRIPTION:
Stream0337 4.0
END DESCRIPTION:
XS GIS Cut Line= 3
        1816425.       13970175.        1817025.       13970525.
      1817524.97     13970375.01
#Sta/Elev= 30
  4305.4 2189.33  4334.8  2187.9  4340.5  2188.1  4377.8 2185.48    4415  2184.7
  4421.2 2183.81  4444.3 2182.74  4452.2 2181.64  4479.5 2179.72  4569.6  2174.3
  4628.3  2171.9  4708.5 2169.52  4714.3  2169.9    4816 2167.56  4906.2 2166.41
    4912 2166.76  4964.9 2164.06  5008.5 2163.43  5008.7 2162.93  5012.2 2162.93
  5012.5 2163.43  5031.3  2164.4  5126.2 2165.55  5302.8 2169.67    5355 2171.44
  5407.2 2175.61  5467.2 2179.13  5480.3 2179.11  5500.3 2180.27    5522 2180.69
#Mann= 3 ,-1 , 0
  4305.4     .07       0  5008.5     .05       0  5012.5     .07       0
Bank Sta=5008.5,5012.5
XS Rating Curve= 0 ,0
Exp/Cntr=0.3,0.1

Type RM Length L Ch R = 1 ,1472    ,482,482,482
BEGIN DESCRIPTION:
Stream0337 3.0
END DESCRIPTION:
XS GIS Cut Line= 3
      1816624.96       13970925.        1817125.       13970975.
      1817425.04     13970874.99
#Sta/Elev= 30
  4497.8  2175.4    4528 2174.98  4545.6 2173.69  4550.6 2173.97  4588.3 2170.29
  4608.4 2169.31  4628.5 2167.67  4651.1 2166.83  4759.1 2163.95  4852.1 2163.71
  4879.7 2164.16  4899.8 2163.29    4930 2162.96  4947.6  2161.3  4980.2 2160.73
  4995.8 2158.27  4996.1 2157.77  4999.6 2157.77  4999.8 2158.27  5010.9 2159.39
  5021.4 2159.46    5032 2160.86  5042.5 2161.17  5095.2 2160.59  5116.3 2161.87
  5137.4 2161.93  5190.1 2165.07  5211.1 2166.92    5306 2170.88  5316.6 2170.96
#Mann= 3 ,-1 , 0
  4497.8     .07       0  4995.8     .05       0  4999.8     .07       0
Bank Sta=4995.8,4999.8
XS Rating Curve= 0 ,0
Exp/Cntr=0.3,0.1

Type RM Length L Ch R = 1 ,990     ,156,156,156
BEGIN DESCRIPTION:
Stream0337 2.0
END DESCRIPTION:
XS GIS Cut Line= 3
      1816825.04     13971375.01        1817125.       13971425.
      1817374.96     13971375.01
#Sta/Elev= 30
  4695.9  2164.6  4766.8 2164.09  4789.6 2163.68  4807.4 2162.76  4817.5 2163.12
  4850.5 2160.66  4858.1 2159.58  4878.3 2158.29    4929 2157.37  4939.2 2156.95
  4949.3 2155.96  4959.4 2156.55  4979.7 2155.36  4989.9 2155.56  4997.5 2154.47
  5008.2 2154.31  5008.4 2153.81  5011.9 2153.81  5012.2 2154.31  5020.4  2155.9
  5030.6 2157.05  5061.2 2157.61    5102 2160.71  5112.2 2160.86  5142.8 2162.49
  5163.2 2162.37  5183.6  2163.2  5214.2 2165.92  5244.7  2167.2  5254.9  2168.3
#Mann= 3 ,-1 , 0
  4695.9     .07       0  5008.2     .05       0  5012.2     .07       0
Bank Sta=5008.2,5012.2
XS Rating Curve= 0 ,0
Exp/Cntr=0.3,0.1

Type RM Length L Ch R = 1 ,834     ,480,480,480
BEGIN DESCRIPTION:
Mapping XS 29a051cb
END DESCRIPTION:
XS GIS Cut Line= 2
      1816613.46     13971575.53       1817716.3     13971586.49
#Sta/Elev= 30
    4488 2169.98  4519.5 2169.59  4629.6 2165.16  4669.6 2165.15  4679.6 2164.49
  4749.6 2162.48  4769.6 2161.46  4819.6 2156.75  4849.6 2155.42  4879.6 2156.16
  4929.6 2154.47  4959.6 2154.68  4969.6 2153.96  4977.6 2151.66  4977.8 2151.16
  4981.3 2151.16  4981.6 2151.66  4989.6 2153.27  4999.6 2152.98  5029.6 2155.88
  5059.6 2156.92  5089.6 2160.37  5109.6 2161.74  5149.6 2162.42  5229.6  2166.3
  5269.6 2167.69  5339.6 2169.01  5529.6 2175.55  5549.6 2176.66  5590.9 2177.47
#Mann= 3 ,-1 , 0
    4488     .07       0  4977.6     .05       0  4981.6     .07       0
Bank Sta=4977.6,4981.6
XS Rating Curve= 0 ,0
Exp/Cntr=0.3,0.1

Type RM Length L Ch R = 1 ,354     ,0,0,0
BEGIN DESCRIPTION:
Stream0337 1.0
END DESCRIPTION:
XS GIS Cut Line= 3
      1816622.03     13971640.02      1816913.05     13971988.09
      1817584.41     13971934.37
#Sta/Elev= 30
  4534.5 2169.27  4582.4  2168.5  4674.7 2165.23  4760.6 2163.64  4845.2 2159.92
  4916.8  2158.1  4931.1 2156.41  4937.6 2154.28  4951.9 2153.82  4958.4 2151.67
  4966.2  2151.9  4972.8 2150.26  4980.5 2150.37  4985.8 2147.68  4991.7 2147.68
  4998.2 2146.29  4998.4 2145.79  5002.2 2146.29  5010.2 2147.84  5020.2 2151.28
  5030.3 2152.17  5130.6 2153.68  5190.8  2156.5    5261 2158.16  5311.2 2160.66
  5481.7 2165.63    5572 2170.18  5602.1 2170.76  5612.1 2171.74  5661.7  2172.5
#Mann= 3 ,-1 , 0
  4534.5     .07       0  4998.2     .05       0  5002.2     .07       0
Bank Sta=4998.2,5002.2
XS Rating Curve= 0 ,0
Exp/Cntr=0.3,0.1

Chan Stop Cuts=-1
Use User Specified Reach Order=0
Composite Channel Slope=5