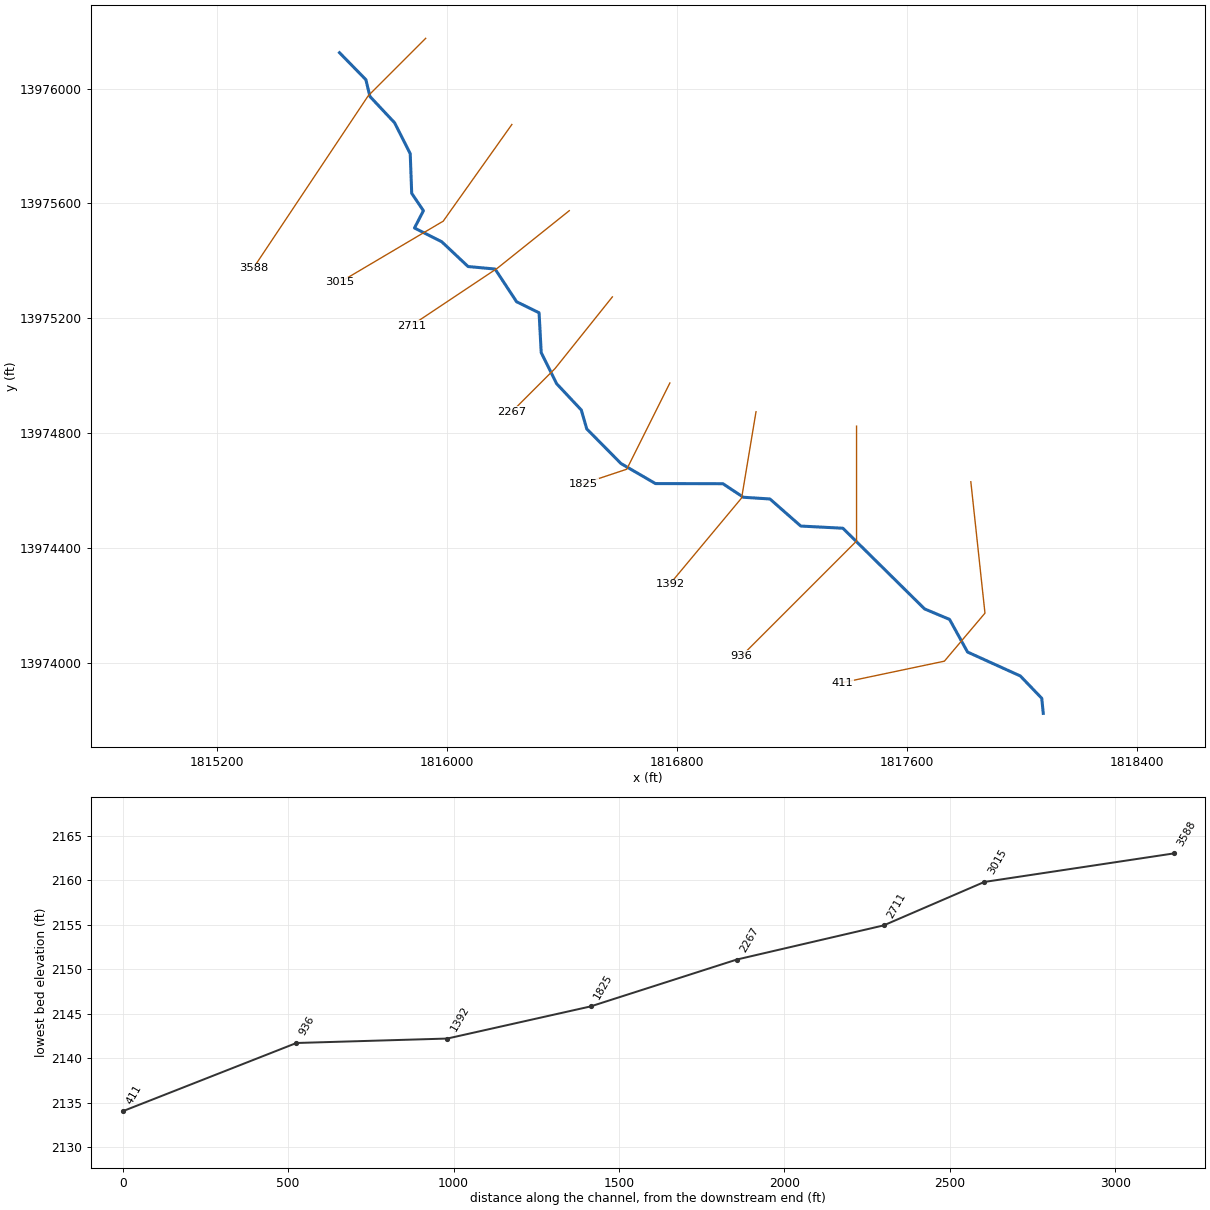
--- Stream0338.prj (project) ---

Proj Title=Stream0338 Base Level Engineering
Current Plan=p01
Default Exp/Contr=0.3,0.1
English Units
Geom File=g01
Flow File=f01
Plan File=p01
Y Axis Title=Elevation
X Axis Title(PF)=Main Channel Distance
X Axis Title(XS)=Station
BEGIN DESCRIPTION:
Stream0338
END DESCRIPTION:
DSS Export Rating Curves= 0
DSS Export Rating Curve Sorted= 0
DSS Export Volume Flow Curves= 0
DXF OffsetX= 0
DXF OffsetY= 0
DXF ScaleX= 1
DXF ScaleY= 10

--- Stream0338.p01 (plan) ---

Plan Title=Multiple Run
Short Identifier=Multiple
Geom File=g01
Flow File=f01
Subcritical Flow
K Sum by GR= 0
Std Step Tol= 0.01
Critical Tol= 0.01
Num of Std Step Trials= 20
Max Error Tol= 0.3
Flow Tol Ratio= 0.001
Split Flow NTrial= 30
Split Flow Tol= 0.02
Split Flow Ratio= 0.02
Log Output Level= 0
Friction Slope Method= 1
Unsteady Friction Slope Method= 2
Unsteady Bridges Friction Slope Method= 1
Parabolic Critical Depth
Global Vel Dist=  1 , 1 , 1
Global Log Level= 0
CheckData=True
Encroach Param= -1, 0, 0, 0
BEGIN DESCRIPTION:
Multiple Run
END DESCRIPTION:

--- Stream0338.f01 (steady flow) ---

Flow Title=Multiple
Program Version=4.10
Number of Profiles= 7
Profile Names=10-year,25-year,50-year,1pct_min,100-year,1pct_plu,500-year
River Rch & RM=Stream0338,Reach-1         ,3588
    1200    2047    2852    1918    3826    7635    6809
Boundary for River Rch & Prof#=Stream0338,Reach-1         , 1
Up Type= 0
Dn Type= 3
Dn Slope=0.009
Boundary for River Rch & Prof#=Stream0338,Reach-1         , 2
Up Type= 0
Dn Type= 3
Dn Slope=0.009
Boundary for River Rch & Prof#=Stream0338,Reach-1         , 3
Up Type= 0
Dn Type= 3
Dn Slope=0.009
Boundary for River Rch & Prof#=Stream0338,Reach-1         , 4
Up Type= 0
Dn Type= 3
Dn Slope=0.009
Boundary for River Rch & Prof#=Stream0338,Reach-1         , 5
Up Type= 0
Dn Type= 3
Dn Slope=0.009
Boundary for River Rch & Prof#=Stream0338,Reach-1         , 6
Up Type= 0
Dn Type= 3
Dn Slope=0.009
Boundary for River Rch & Prof#=Stream0338,Reach-1         , 7
Up Type= 0
Dn Type= 3
Dn Slope=0.009
DSS Import GetInterval= 0
DSS Import GetPeak= 0
DSS Import FillOption= 0

--- Stream0338.g01 (geometry) ---

Geom Title=Existing Conditions

River Reach=Stream0338,Reach-1
Reach XY= 30
      1815625.00     13976125.00      1815716.89     13976031.07
      1815730.86     13975972.71      1815816.84     13975881.05
      1815871.24     13975773.44      1815876.39     13975635.44
      1815917.19     13975574.89      1815886.11     13975514.68
      1815981.00     13975466.82      1816072.64     13975380.56
      1816166.66     13975371.83      1816241.52     13975257.97
      1816319.81     13975219.56      1816327.25     13975080.94
      1816380.84     13974972.71      1816466.82     13974881.04
      1816485.78     13974815.32      1816604.90     13974694.76
      1816725.00     13974625.00      1816959.78     13974624.48
      1817030.98     13974577.36      1817123.50     13974571.38
      1817230.86     13974477.08      1817377.45     13974469.53
      1817661.80     13974188.64      1817748.83     13974152.13
      1817811.44     13974038.48      1817995.13     13973955.25
      1818069.70     13973877.54      1818075.00     13973825.00

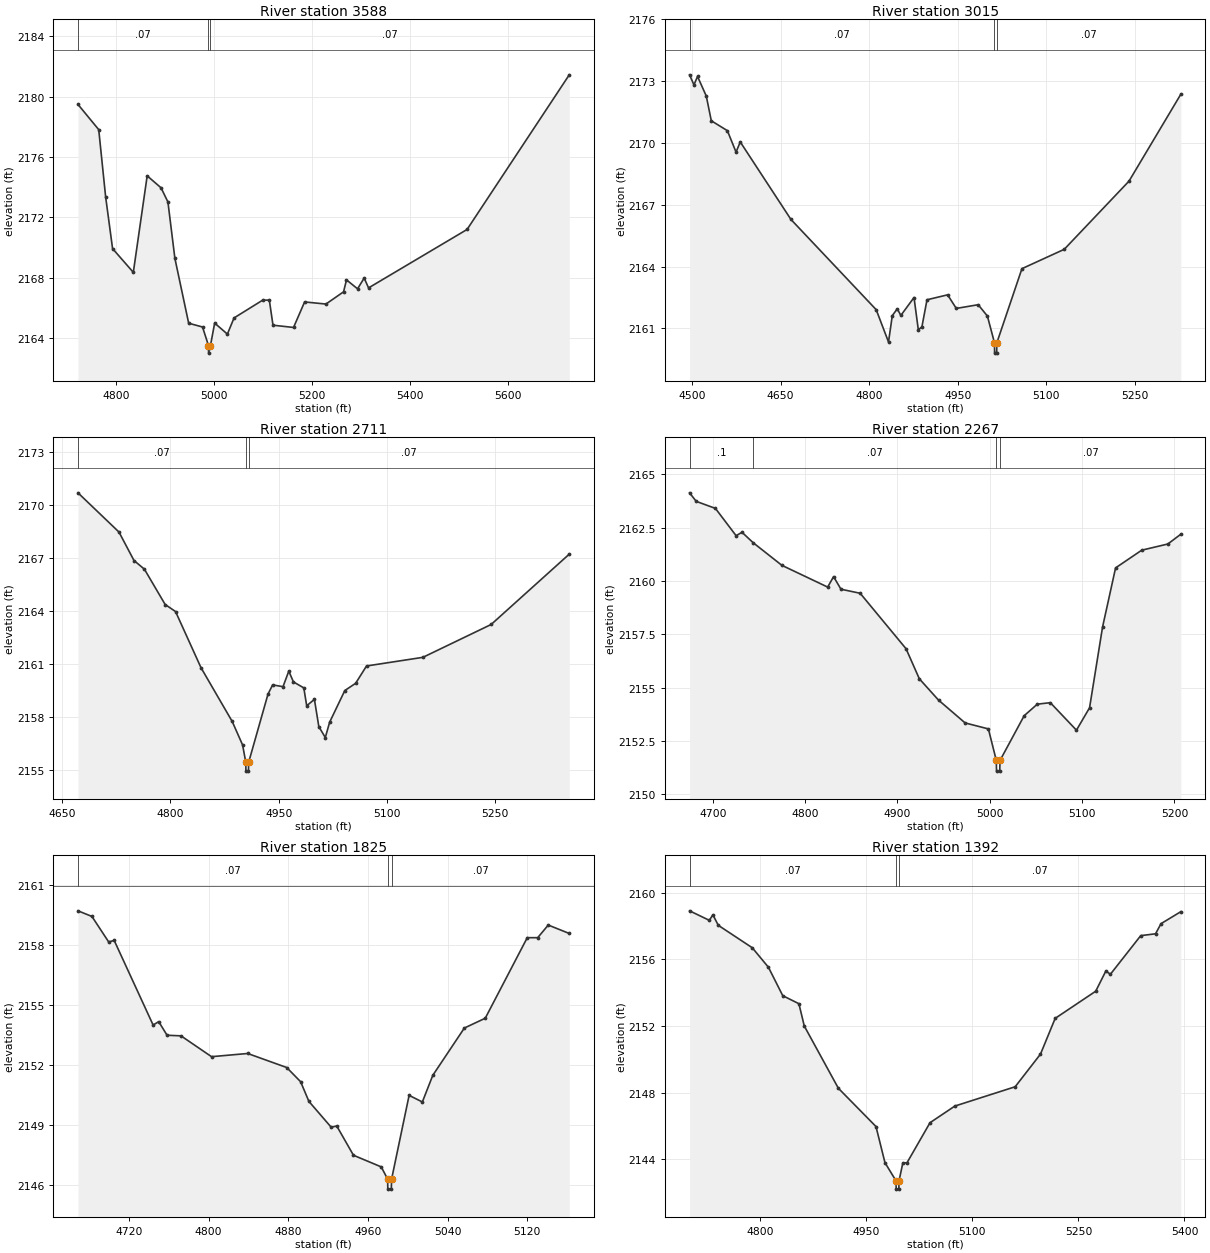
Type RM Length L Ch R = 1,3588,573,573,573
BEGIN DESCRIPTION:
Stream0338 7.0
END DESCRIPTION:
XS GIS Cut Line= 3
      1815924.97     13976174.97      1815725.00     13975975.00
      1815325.01     13975375.01
#Sta/Elev= 30
  4722.0 2179.48  4764.4 2177.81  4778.5 2173.36  4792.7 2169.93  4835.1 2168.36
  4863.4 2174.75  4891.7 2173.96  4905.8 2173.02  4920.0 2169.29  4948.2 2164.99
  4976.5 2164.74  4988.7 2163.51  4988.9 2163.01  4992.7 2163.51  5001.3 2165.00
  5027.3 2164.27  5040.9 2165.34  5099.5 2166.52  5113.0 2166.52  5120.5 2164.86
  5162.5 2164.71  5185.1 2166.40  5228.7 2166.26  5264.7 2167.07  5270.7 2167.86
  5293.3 2167.27  5306.8 2167.98  5315.8 2167.33  5517.1 2171.20  5725.9 2181.44
#Mann=3,-1,0
  4722.0    0.07       0  4988.7    0.05       0  4992.7    0.07       0
Bank Sta=4988.7,4992.7
Exp/Cntr=0.3,0.1

Type RM Length L Ch R = 1,3015,304,304,304
BEGIN DESCRIPTION:
Stream0338 6.0
END DESCRIPTION:
XS GIS Cut Line= 3
      1816225.00     13975875.01      1815986.06     13975538.54
      1815624.96     13975324.98
#Sta/Elev= 30
  4495.7 2173.31  4503.1 2172.82  4509.2 2173.23  4524.0 2172.28  4532.5 2171.08
  4559.7 2170.60  4574.4 2169.56  4581.6 2170.05  4667.4 2166.29  4811.8 2161.91
  4832.7 2160.34  4839.1 2161.62  4847.5 2161.95  4853.6 2161.63  4875.9 2162.50
  4883.2 2160.93  4889.3 2161.08  4897.9 2162.39  4932.8 2162.63  4947.5 2161.97
  4984.6 2162.15  5000.2 2161.60  5012.2 2160.30  5012.4 2159.80  5015.9 2159.80
  5016.2 2160.30  5058.7 2163.90  5130.4 2164.84  5240.1 2168.15  5327.9 2172.37
#Mann=3,-1,0
  4495.7    0.07       0  5012.2    0.05       0  5016.2    0.07       0
Bank Sta=5012.2,5016.2
Exp/Cntr=0.3,0.1

Type RM Length L Ch R = 1,2711,444,444,444
BEGIN DESCRIPTION:
Stream0338 5.0
END DESCRIPTION:
XS GIS Cut Line= 3
      1816424.98     13975574.99      1816175.00     13975375.00
      1815874.99     13975174.99
#Sta/Elev= 30
  4671.9 2170.67  4728.7 2168.45  4749.5 2166.84  4763.9 2166.35  4792.7 2164.35
  4807.1 2163.95  4842.4 2160.77  4885.6 2157.73  4900.0 2156.40  4904.4 2155.42
  4904.6 2154.92  4908.1 2154.92  4908.4 2155.42  4935.2 2159.28  4941.6 2159.80
  4956.0 2159.70  4964.0 2160.58  4970.4 2159.97  4984.8 2159.63  4988.8 2158.62
  4999.5 2158.98  5005.6 2157.44  5014.6 2156.82  5020.6 2157.69  5041.6 2159.48
  5056.6 2159.89  5071.7 2160.87  5149.8 2161.36  5244.4 2163.22  5352.6 2167.20
#Mann=3,-1,0
  4671.9    0.07       0  4904.4    0.05       0  4908.4    0.07       0
Bank Sta=4904.4,4908.4
Exp/Cntr=0.3,0.1

Type RM Length L Ch R = 1,2267,442,442,442
BEGIN DESCRIPTION:
Stream0338 4.0
END DESCRIPTION:
XS GIS Cut Line= 3
      1816574.97     13975274.97      1816375.00     13975025.00
      1816225.03     13974875.03
#Sta/Elev= 30
  4674.8 2164.13  4682.0 2163.73  4702.8 2163.40  4725.2 2162.12  4731.6 2162.28
  4743.7 2161.79  4774.8 2160.73  4824.4 2159.71  4830.8 2160.20  4838.8 2159.61
  4859.6 2159.42  4909.3 2156.82  4923.7 2155.41  4944.5 2154.41  4973.3 2153.34
  4998.5 2153.06  5007.1 2151.58  5007.3 2151.08  5010.8 2151.08  5011.1 2151.58
  5037.3 2153.68  5051.5 2154.22  5065.6 2154.29  5093.9 2153.00  5108.1 2154.05
  5122.2 2157.84  5136.3 2160.61  5164.6 2161.44  5192.9 2161.73  5207.0 2162.19
#Mann=4,-1,0
  4674.8     0.1       0  4743.7    0.07       0  5007.1    0.05       0
  5011.1    0.07       0
Bank Sta=5007.1,5011.1
Exp/Cntr=0.3,0.1

Type RM Length L Ch R = 1,1825,433,433,433
BEGIN DESCRIPTION:
Stream0338 3.0
END DESCRIPTION:
XS GIS Cut Line= 3
      1816775.02     13974975.04      1816625.00     13974675.00
      1816474.97     13974624.99
#Sta/Elev= 30
  4668.7 2159.70  4682.7 2159.42  4699.5 2158.15  4705.1 2158.22  4744.2 2154.00
  4749.8 2154.17  4758.2 2153.49  4772.2 2153.46  4802.9 2152.42  4839.2 2152.58
  4878.4 2151.88  4892.4 2151.17  4900.7 2150.19  4923.1 2148.90  4928.7 2148.96
  4945.5 2147.50  4973.4 2146.92  4979.8 2146.31  4980.0 2145.81  4983.5 2145.81
  4983.8 2146.31  5001.4 2150.49  5014.7 2150.16  5025.2 2151.49  5056.9 2153.85
  5077.9 2154.34  5120.1 2158.36  5130.6 2158.36  5141.2 2158.99  5162.3 2158.57
#Mann=3,-1,0
  4668.7    0.07       0  4979.8    0.05       0  4983.8    0.07       0
Bank Sta=4979.8,4983.8
Exp/Cntr=0.3,0.1

Type RM Length L Ch R = 1,1392,456,456,456
BEGIN DESCRIPTION:
Stream0338 2.0
END DESCRIPTION:
XS GIS Cut Line= 3
      1817075.00     13974875.02      1817025.00     13974575.00
      1816774.98     13974274.98
#Sta/Elev= 30
  4700.2 2158.92  4728.1 2158.35  4733.2 2158.68  4740.8 2158.05  4788.9 2156.70
  4811.7 2155.53  4832.0 2153.82  4854.8 2153.34  4862.4 2152.00  4910.6 2148.26
  4963.8 2145.96  4976.5 2143.79  4992.1 2142.70  4992.4 2142.20  4996.1 2142.20
  4996.4 2142.70  5001.8 2143.78  5007.6 2143.78  5040.2 2146.19  5075.3 2147.19
  5160.6 2148.35  5196.4 2150.31  5217.2 2152.46  5274.5 2154.09  5288.8 2155.30
  5295.3 2155.11  5338.2 2157.43  5359.1 2157.54  5366.9 2158.15  5394.9 2158.87
#Mann=3,-1,0
  4700.2    0.07       0  4992.1    0.05       0  4996.4    0.07       0
Bank Sta=4992.1,4996.4
Exp/Cntr=0.3,0.1

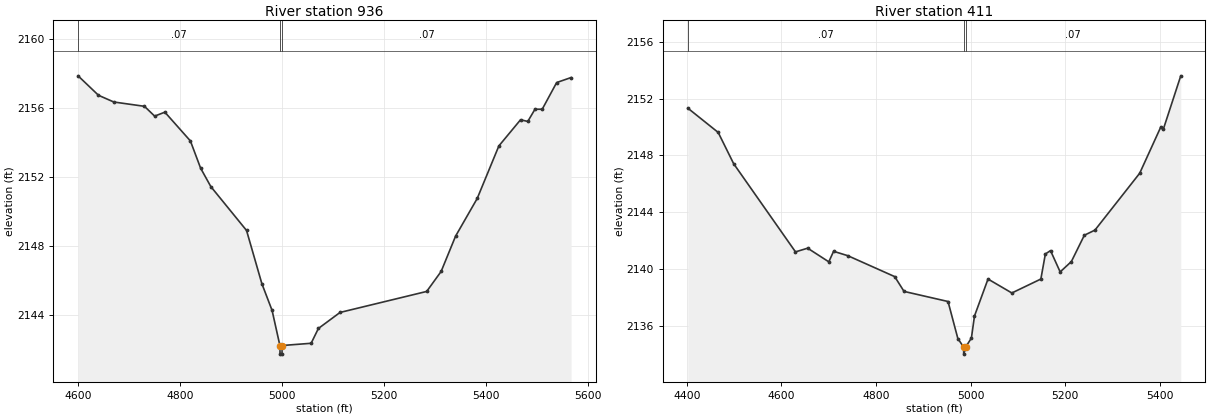
Type RM Length L Ch R = 1,936,525,525,525
BEGIN DESCRIPTION:
Stream0338 1.0
END DESCRIPTION:
XS GIS Cut Line= 3
      1817425.00     13974824.96      1817425.00     13974425.00
      1817025.03     13974025.03
#Sta/Elev= 30
  4600.4 2157.86  4640.4 2156.73  4670.4 2156.34  4730.4 2156.09  4750.4 2155.52
  4770.4 2155.75  4820.4 2154.08  4840.4 2152.50  4860.4 2151.43  4930.4 2148.88
  4960.4 2145.79  4980.4 2144.24  4995.7 2142.20  4996.0 2141.70  4999.8 2141.70
  5000.1 2142.20  5056.9 2142.33  5071.1 2143.19  5113.5 2144.12  5283.2 2145.34
  5311.5 2146.50  5339.8 2148.55  5382.2 2150.74  5424.6 2153.79  5467.1 2155.31
  5481.2 2155.21  5495.3 2155.92  5509.5 2155.92  5537.8 2157.47  5566.0 2157.76
#Mann=3,-1,0
  4600.4    0.07       0  4995.7    0.05       0  5000.1    0.07       0
Bank Sta=4995.7,5000.1
Exp/Cntr=0.3,0.1

Type RM Length L Ch R = 1,411,0,0,0
BEGIN DESCRIPTION:
Stream0338 0.0
END DESCRIPTION:
XS GIS Cut Line= 4
      1817822.86     13974631.44      1817872.06     13974173.92
      1817730.74     13974006.71      1817375.60     13973932.01
#Sta/Elev= 30
  4402.0 2151.33  4466.3 2149.62  4499.0 2147.42  4629.7 2141.22  4655.4 2141.48
  4700.1 2140.52  4710.2 2141.26  4740.4 2140.95  4839.4 2139.48  4859.1 2138.44
  4952.1 2137.73  4972.9 2135.12  4985.0 2134.53  4985.3 2134.03  4989.4 2134.53
  5001.5 2135.16  5008.0 2136.71  5036.6 2139.31  5087.0 2138.33  5148.3 2139.31
  5157.8 2141.07  5168.7 2141.31  5189.1 2139.81  5212.8 2140.54  5240.2 2142.39
  5262.6 2142.75  5357.2 2146.75  5401.9 2150.01  5407.0 2149.83  5444.0 2153.60
#Mann=3,-1,0
  4402.0    0.07       0  4985.0    0.05       0  4989.4    0.07       0
Bank Sta=4985,4989.4
Exp/Cntr=0.3,0.1

Chan Stop Cuts=-1