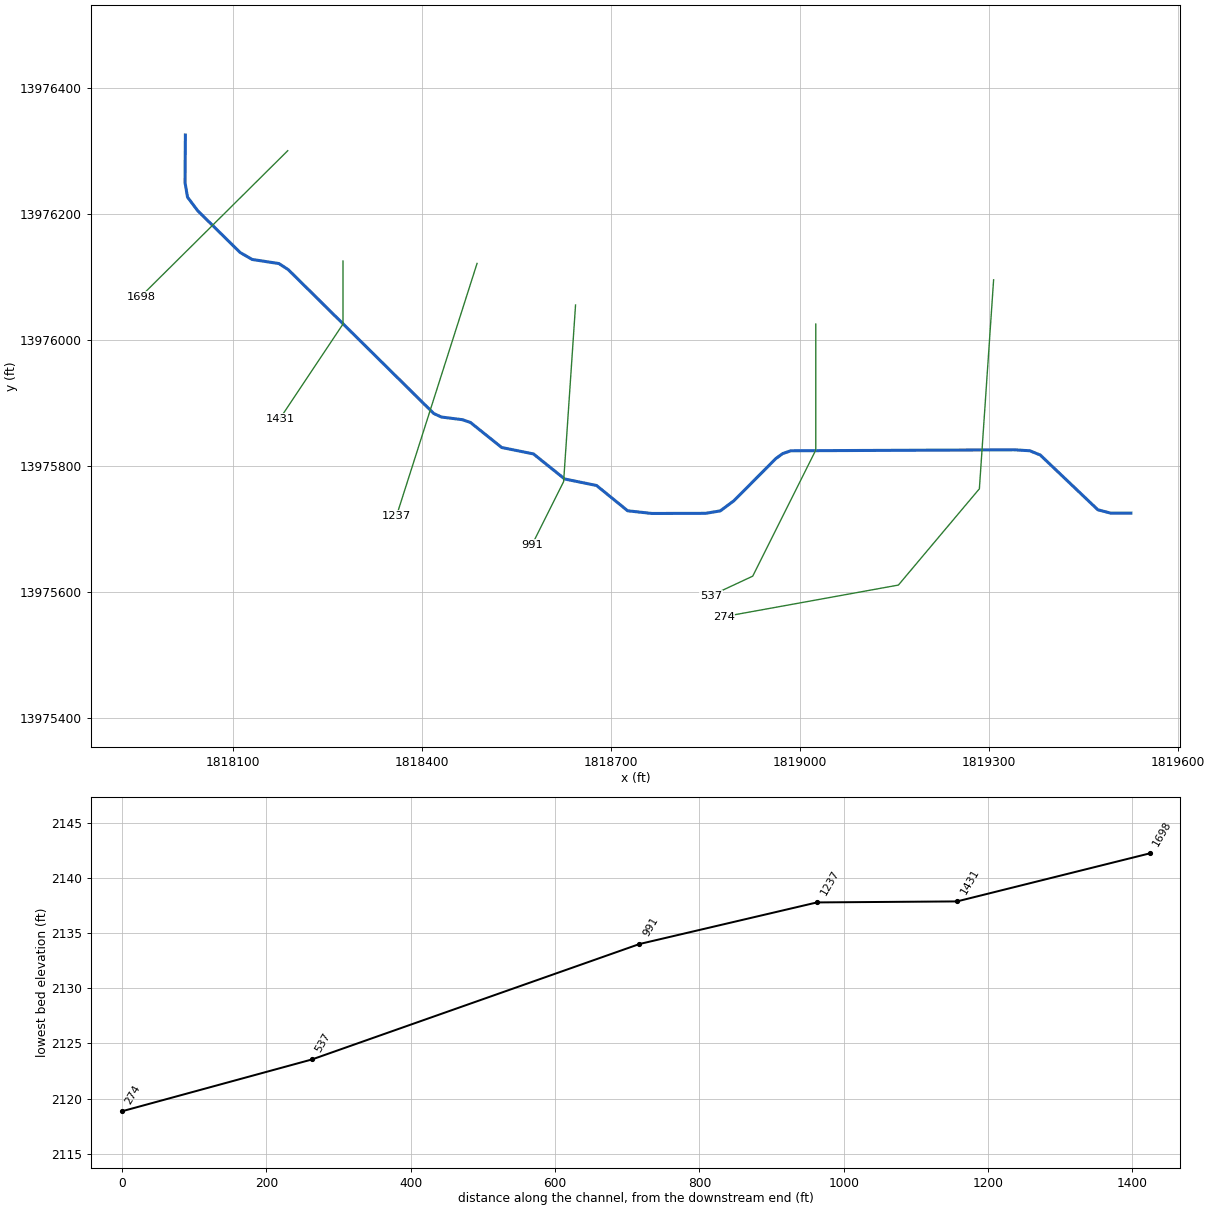
--- Stream0340.prj (project) ---

Proj Title=Stream0340 Base Level Engineering
Current Plan=p01
Default Exp/Contr=0.3,0.1
English Units
Geom File=g01
Flow File=f01
Plan File=p01
Y Axis Title=Elevation
X Axis Title(PF)=Main Channel Distance
X Axis Title(XS)=Station
BEGIN DESCRIPTION:
Stream0340
END DESCRIPTION:
DSS Export Rating Curves= 0
DSS Export Rating Curve Sorted= 0
DSS Export Volume Flow Curves= 0
DXF OffsetX= 0
DXF OffsetY= 0
DXF ScaleX= 1
DXF ScaleY= 10

--- Stream0340.p01 (plan) ---

Plan Title=Multiple Run
Short Identifier=Multiple
Geom File=g01
Flow File=f01
Subcritical Flow
K Sum by GR= 0
Std Step Tol= 0.01
Critical Tol= 0.01
Num of Std Step Trials= 20
Max Error Tol= 0.3
Flow Tol Ratio= 0.001
Split Flow NTrial= 30
Split Flow Tol= 0.02
Split Flow Ratio= 0.02
Log Output Level= 0
Friction Slope Method= 1
Unsteady Friction Slope Method= 2
Unsteady Bridges Friction Slope Method= 1
Parabolic Critical Depth
Global Vel Dist=  1 , 1 , 1
Global Log Level= 0
CheckData=True
Encroach Param= -1, 0, 0, 0
BEGIN DESCRIPTION:
Multiple Run
END DESCRIPTION:

--- Stream0340.f01 (steady flow) ---

Flow Title=Multiple
Program Version=4.10
Number of Profiles= 7
Profile Names=10-year,25-year,50-year,1pct_min,100-year,1pct_plu,500-year
River Rch & RM=Stream0340,Reach-1         ,1698
     564     923    1252     822    1641    3274    2782
Boundary for River Rch & Prof#=Stream0340,Reach-1         , 1
Up Type= 0
Dn Type= 3
Dn Slope=0.01
Boundary for River Rch & Prof#=Stream0340,Reach-1         , 2
Up Type= 0
Dn Type= 3
Dn Slope=0.01
Boundary for River Rch & Prof#=Stream0340,Reach-1         , 3
Up Type= 0
Dn Type= 3
Dn Slope=0.01
Boundary for River Rch & Prof#=Stream0340,Reach-1         , 4
Up Type= 0
Dn Type= 3
Dn Slope=0.01
Boundary for River Rch & Prof#=Stream0340,Reach-1         , 5
Up Type= 0
Dn Type= 3
Dn Slope=0.01
Boundary for River Rch & Prof#=Stream0340,Reach-1         , 6
Up Type= 0
Dn Type= 3
Dn Slope=0.01
Boundary for River Rch & Prof#=Stream0340,Reach-1         , 7
Up Type= 0
Dn Type= 3
Dn Slope=0.01
DSS Import GetInterval= 0
DSS Import GetPeak= 0
DSS Import FillOption= 0

--- Stream0340.g01 (geometry) ---

Geom Title=Existing Conditions

River Reach=Stream0340,Reach-1
Reach XY= 30
      1818025.00     13976325.00      1818024.40     13976249.75
      1818028.38     13976226.39      1818044.60     13976204.80
      1818111.76     13976138.62      1818131.04     13976127.53
      1818173.35     13976121.02      1818188.21     13976111.37
      1818418.94     13975883.14      1818431.03     13975877.50
      1818464.30     13975873.30      1818477.19     13975868.90
      1818526.72     13975829.16      1818577.20     13975818.92
      1818626.72     13975779.16      1818677.18     13975768.88
      1818726.56     13975728.74      1818764.83     13975724.49
      1818850.11     13975724.68      1818873.53     13975728.54
      1818895.14     13975744.65      1818961.69     13975811.60
      1818972.55     13975819.52      1818985.44     13975823.94
      1819340.20     13975825.49      1819364.57     13975823.95
      1819381.19     13975817.19      1819472.49     13975730.33
      1819493.12     13975724.93      1819525.00     13975725.00

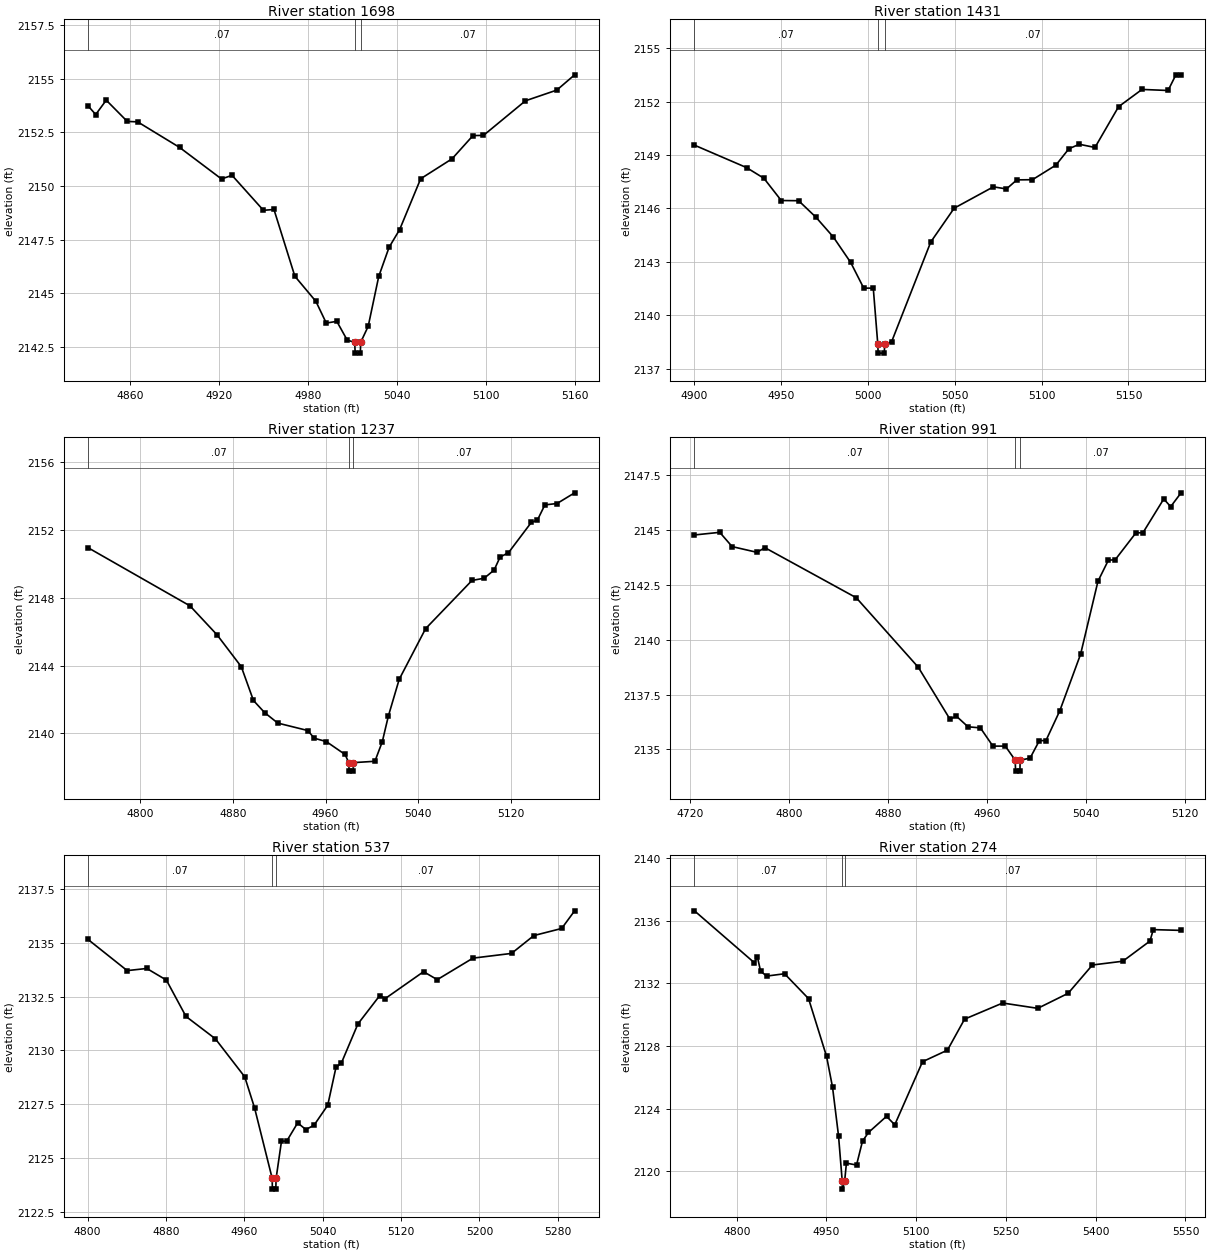
Type RM Length L Ch R = 1,1698,267,267,267
BEGIN DESCRIPTION:
Stream0340 4.0
END DESCRIPTION:
XS GIS Cut Line= 2
      1818187.34     13976300.09      1817954.26     13976068.74
#Sta/Elev= 30
  4831.6 2153.74  4836.8 2153.33  4843.9 2154.00  4858.1 2153.01  4865.1 2152.99
  4893.4 2151.80  4921.7 2150.33  4928.8 2150.50  4950.0 2148.87  4957.1 2148.91
  4971.2 2145.80  4985.4 2144.63  4992.4 2143.62  4999.5 2143.70  5006.5 2142.83
  5011.6 2142.72  5011.9 2142.22  5015.4 2142.22  5015.6 2142.72  5020.7 2143.47
  5027.8 2145.79  5034.8 2147.15  5041.9 2147.97  5056.1 2150.34  5077.3 2151.27
  5091.4 2152.35  5098.5 2152.36  5126.8 2153.97  5148.0 2154.47  5160.0 2155.18
#Mann=3,-1,0
  4831.6    0.07       0  5011.6    0.05       0  5015.6    0.07       0
Bank Sta=5011.6,5015.6
Exp/Cntr=0.3,0.1

Type RM Length L Ch R = 1,1431,194,194,194
BEGIN DESCRIPTION:
Stream0340 3.0
END DESCRIPTION:
XS GIS Cut Line= 3
      1818275.00     13976125.04      1818275.00     13976025.00
      1818175.01     13975875.02
#Sta/Elev= 30
  4900.0 2149.55  4930.0 2148.29  4940.0 2147.69  4950.0 2146.44  4960.0 2146.43
  4970.0 2145.50  4980.0 2144.39  4990.0 2142.96  4997.5 2141.52  5003.0 2141.52
  5005.6 2138.37  5005.8 2137.87  5009.3 2137.87  5009.6 2138.37  5013.6 2138.52
  5036.1 2144.11  5049.6 2146.01  5072.2 2147.21  5079.7 2147.09  5085.7 2147.60
  5094.7 2147.61  5108.2 2148.43  5115.7 2149.35  5121.7 2149.60  5130.7 2149.42
  5144.3 2151.71  5157.8 2152.68  5172.8 2152.62  5177.3 2153.50  5180.3 2153.50
#Mann=3,-1,0
  4900.0    0.07       0  5005.6    0.05       0  5009.6    0.07       0
Bank Sta=5005.6,5009.6
Exp/Cntr=0.3,0.1

Type RM Length L Ch R = 1,1237,246,246,246
BEGIN DESCRIPTION:
Stream0340 5.0
END DESCRIPTION:
XS GIS Cut Line= 2
      1818487.67     13976121.23      1818359.86     13975720.52
#Sta/Elev= 30
  4754.7 2150.94  4842.9 2147.51  4866.2 2145.81  4887.2 2143.93  4897.7 2141.94
  4907.3 2141.23  4918.7 2140.61  4944.7 2140.17  4950.2 2139.72  4960.7 2139.52
  4976.9 2138.76  4980.1 2138.28  4980.4 2137.78  4983.9 2137.78  4984.1 2138.28
  5002.7 2138.36  5009.1 2139.52  5014.3 2141.02  5023.7 2143.19  5046.5 2146.17
  5086.6 2149.01  5097.1 2149.14  5105.7 2149.62  5110.9 2150.39  5118.1 2150.64
  5137.9 2152.43  5143.1 2152.56  5149.6 2153.46  5160.1 2153.54  5175.3 2154.17
#Mann=3,-1,0
  4754.7    0.07       0  4980.1    0.05       0  4984.1    0.07       0
Bank Sta=4980.1,4984.1
Exp/Cntr=0.3,0.1

Type RM Length L Ch R = 1,991,454,454,454
BEGIN DESCRIPTION:
Stream0340 2.0
END DESCRIPTION:
XS GIS Cut Line= 3
      1818643.93     13976055.31      1818625.00     13975775.00
      1818574.98     13975674.96
#Sta/Elev= 30
  4723.9 2144.77  4744.3 2144.89  4754.3 2144.24  4774.3 2143.98  4780.8 2144.19
  4854.5 2141.91  4904.6 2138.74  4930.2 2136.37  4935.2 2136.52  4944.7 2136.03
  4954.7 2135.98  4964.8 2135.15  4974.8 2135.15  4982.8 2134.51  4983.1 2134.01
  4986.6 2134.01  4986.8 2134.51  4994.8 2134.60  5002.3 2135.40  5007.6 2135.40
  5018.8 2136.76  5035.6 2139.34  5049.6 2142.66  5058.0 2143.62  5063.5 2143.64
  5080.3 2144.87  5085.9 2144.87  5102.7 2146.41  5108.3 2146.06  5116.7 2146.69
#Mann=3,-1,0
  4723.9    0.07       0  4982.8    0.05       0  4986.8    0.07       0
Bank Sta=4982.8,4986.8
Exp/Cntr=0.3,0.1

Type RM Length L Ch R = 1,537,263,263,263
BEGIN DESCRIPTION:
Stream0340 1.0
END DESCRIPTION:
XS GIS Cut Line= 4
      1819025.00     13976025.00      1819025.00     13975825.00
      1818925.00     13975625.00      1818858.76     13975594.09
#Sta/Elev= 30
  4800.4 2135.16  4840.4 2133.71  4860.4 2133.81  4880.4 2133.27  4900.4 2131.58
  4930.4 2130.54  4960.4 2128.77  4970.4 2127.33  4988.4 2124.05  4988.6 2123.55
  4992.1 2123.55  4992.4 2124.05  4997.9 2125.78  5003.2 2125.78  5014.4 2126.63
  5022.8 2126.32  5031.1 2126.52  5045.1 2127.45  5053.5 2129.21  5059.1 2129.42
  5075.9 2131.23  5098.2 2132.55  5103.8 2132.41  5142.9 2133.66  5156.9 2133.29
  5193.3 2134.29  5232.7 2134.51  5255.5 2135.34  5283.9 2135.67  5297.1 2136.49
#Mann=3,-1,0
  4800.4    0.07       0  4988.4    0.05       0  4992.4    0.07       0
Bank Sta=4988.4,4992.4
Exp/Cntr=0.3,0.1

Type RM Length L Ch R = 1,274,0,0,0
BEGIN DESCRIPTION:
Stream0340 0.0
END DESCRIPTION:
XS GIS Cut Line= 4
      1819307.13     13976095.25      1819284.55     13975763.63
      1819156.08     13975610.85      1818879.20     13975560.67
#Sta/Elev= 30
  4729.3 2136.64  4829.5 2133.32  4834.5 2133.70  4839.8 2132.79  4849.8 2132.47
  4879.9 2132.62  4920.0 2131.03  4950.1 2127.34  4960.1 2125.37  4970.1 2122.27
  4976.3 2119.36  4976.6 2118.86  4980.3 2119.36  4983.3 2120.52  5000.2 2120.40
  5010.2 2121.93  5020.2 2122.48  5050.3 2123.51  5064.1 2122.97  5110.5 2127.00
  5152.2 2127.74  5180.8 2129.72  5244.5 2130.75  5303.1 2130.41  5353.9 2131.37
  5394.5 2133.18  5445.3 2133.42  5490.7 2134.71  5496.2 2135.44  5542.7 2135.39
#Mann=3,-1,0
  4729.3    0.07       0  4976.3    0.05       0  4980.3    0.07       0
Bank Sta=4976.3,4980.3
Exp/Cntr=0.3,0.1

Chan Stop Cuts=-1