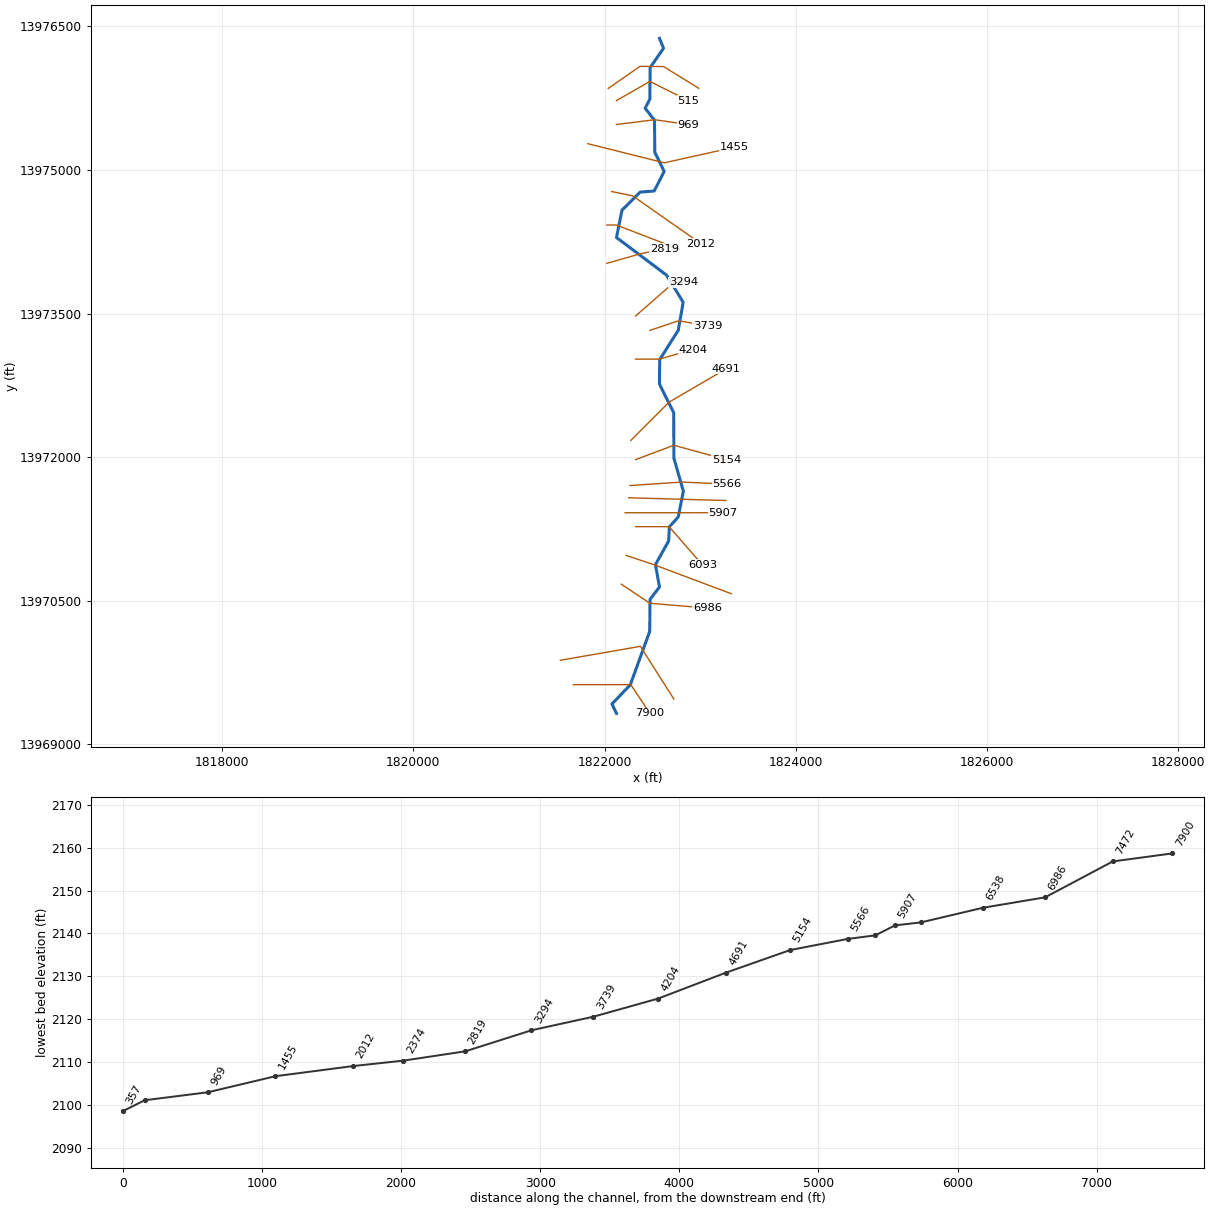
--- Stream0341.prj (project) ---

Proj Title=Stream0341 Base Level Engineering
Current Plan=p01
Default Exp/Contr=0.3,0.1
English Units
Geom File=g01
Flow File=f01
Plan File=p01
BEGIN DESCRIPTION:
Stream0341
END DESCRIPTION:

--- Stream0341.p01 (plan) ---

Plan Title=Multiple Run
Short Identifier=Multiple
Geom File=g01
Flow File=f01
Subcritical Flow
K Sum by GR= 0
Std Step Tol= 0.01
Critical Tol= 0.01
Num of Std Step Trials= 20
Max Error Tol= 0.3
Flow Tol Ratio= 0.001
Split Flow NTrial= 30
Split Flow Tol= 0.02
Split Flow Ratio= 0.02
Log Output Level= 0
Friction Slope Method= 1
Unsteady Friction Slope Method= 2
Unsteady Bridges Friction Slope Method= 1
Parabolic Critical Depth
Global Vel Dist=  1 , 1 , 1
Global Log Level= 0
CheckData=True
Encroach Param= -1, 0, 0, 0
BEGIN DESCRIPTION:
Multiple Run
END DESCRIPTION:

--- Stream0341.f01 (steady flow) ---

Flow Title=Multiple
Number of Profiles=7
Profile Names=10-year,25-year,50-year,1pct_min,100-year,1pct_plu,500-year
River Rch & RM= Stream0341,Reach-1,7900
    1231    2098    2920    1959    3909    7800    6933
River Rch & RM= Stream0341,Reach-1,6538
    1704    2950    4147    2808    5604   11181   10123
Boundary for River Rch & Prof#=Stream0341,Reach-1,1
Up Type=0
Dn Type=3
Dn Slope=0.005
Boundary for River Rch & Prof#=Stream0341,Reach-1,2
Up Type=0
Dn Type=3
Dn Slope=0.005
Boundary for River Rch & Prof#=Stream0341,Reach-1,3
Up Type=0
Dn Type=3
Dn Slope=0.005
Boundary for River Rch & Prof#=Stream0341,Reach-1,4
Up Type=0
Dn Type=3
Dn Slope=0.005
Boundary for River Rch & Prof#=Stream0341,Reach-1,5
Up Type=0
Dn Type=3
Dn Slope=0.005
Boundary for River Rch & Prof#=Stream0341,Reach-1,6
Up Type=0
Dn Type=3
Dn Slope=0.005
Boundary for River Rch & Prof#=Stream0341,Reach-1,7
Up Type=0
Dn Type=3
Dn Slope=0.005

--- Stream0341.g01 (geometry) ---

Geom Title=Existing Conditions

River Reach=Stream0341,Reach-1
Reach XY= 30
      1822125.00     13969325.00      1822078.07     13969423.42
      1822269.48     13969622.57      1822472.76     13970180.93
      1822476.06     13970514.56      1822575.04     13970644.99
      1822533.04     13970878.32      1822671.24     13971126.56
      1822678.56     13971273.53      1822771.45     13971376.47
      1822825.09     13971645.10      1822725.52     13971990.22
      1822723.80     13972464.50      1822574.54     13972764.81
      1822577.24     13973019.07      1822771.38     13973326.50
      1822822.77     13973619.07      1822648.51     13973902.01
      1822124.95     13974294.98      1822183.14     13974581.06
      1822372.56     13974769.53      1822519.59     13974780.18
      1822623.92     13974985.55      1822526.06     13975185.44
      1822522.93     13975519.14      1822424.61     13975645.13
      1822474.46     13975740.21      1822477.24     13976069.07
      1822617.40     13976271.62      1822575.00     13976375.00

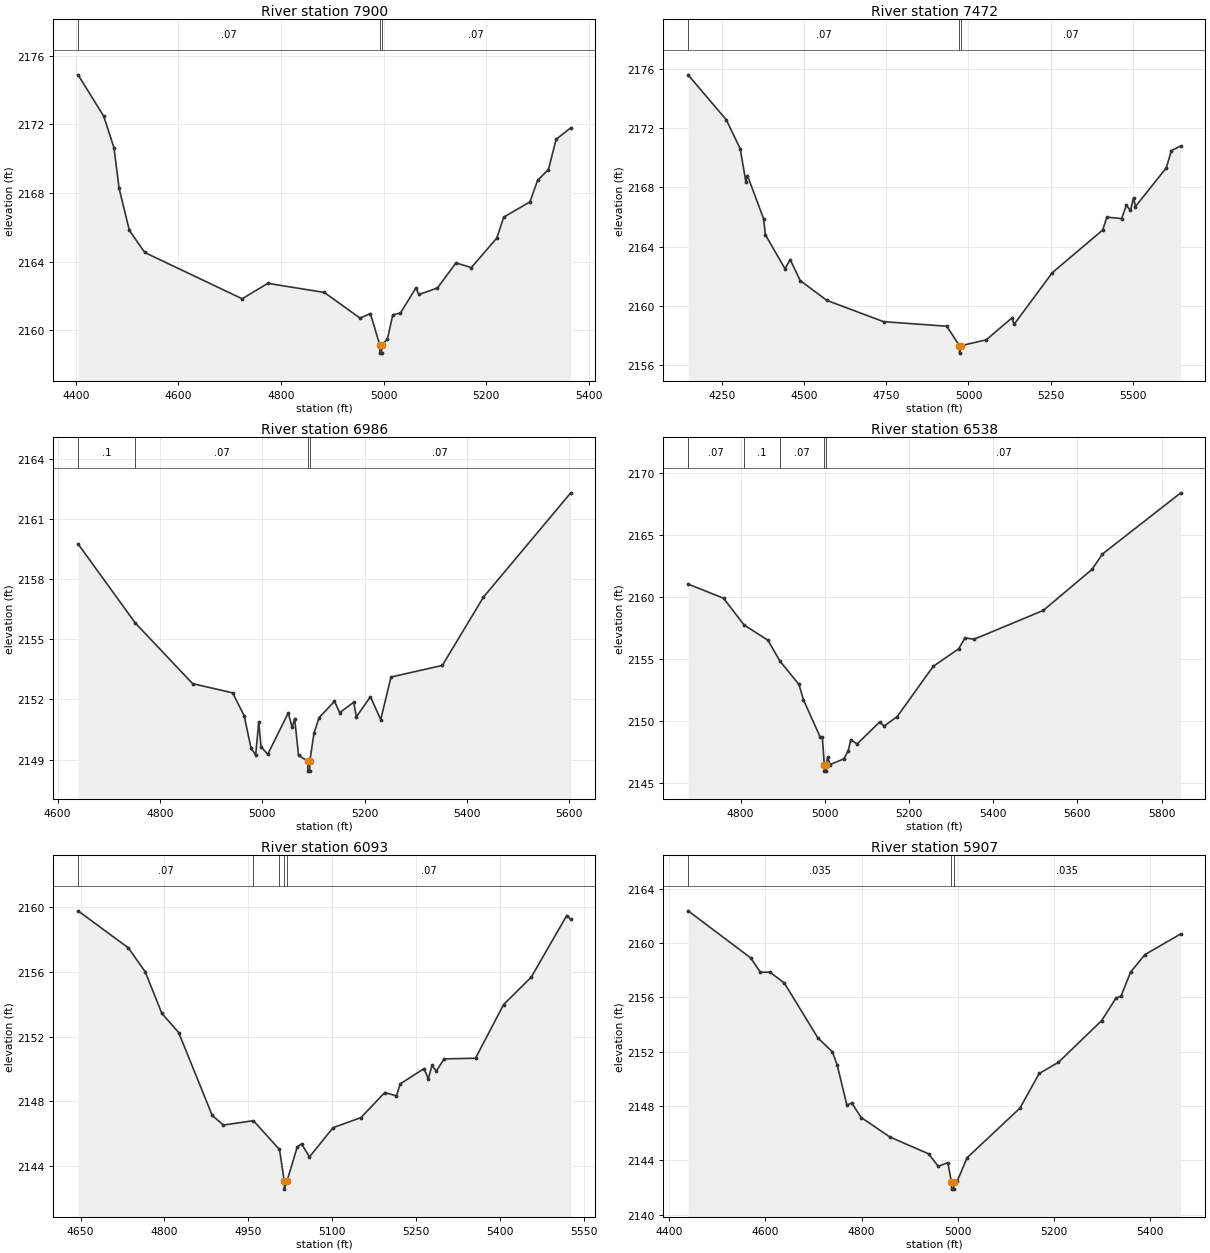
Type RM Length L Ch R = 1,7900,428,428,428
BEGIN DESCRIPTION:
Stream0341 17.0
END DESCRIPTION:
XS GIS Cut Line= 3
      1821674.96     13969625.00      1822275.00     13969625.00
      1822475.00     13969325.00
#Sta/Elev= 30
  4404.3 2174.89  4454.3 2172.48  4474.3 2170.64  4484.3 2168.28  4504.3 2165.82
  4534.3 2164.53  4724.3 2161.83  4774.3 2162.73  4884.3 2162.20  4954.3 2160.70
  4974.3 2160.97  4992.3 2159.16  4992.6 2158.66  4996.1 2158.66  4996.3 2159.16
  5007.3 2159.46  5017.9 2160.89  5032.9 2161.00  5062.9 2162.46  5068.9 2162.08
  5105.0 2162.46  5141.1 2163.92  5171.1 2163.65  5220.7 2165.37  5234.2 2166.59
  5285.3 2167.48  5300.3 2168.74  5321.3 2169.36  5336.4 2171.13  5364.9 2171.80
#Mann=3,-1,0
  4404.3    0.07       0  4992.3    0.05       0  4996.3    0.07       0
Bank Sta=4992.3,4996.3
Exp/Cntr=0.3,0.1

Type RM Length L Ch R = 1,7472,486,486,486
BEGIN DESCRIPTION:
Stream0341 16.0
END DESCRIPTION:
XS GIS Cut Line= 3
      1821538.54     13969879.54      1822375.00     13970025.00
      1822724.98     13969475.03
#Sta/Elev= 30
  4145.8 2175.62  4262.1 2172.58  4304.6 2170.62  4321.7 2168.39  4326.8 2168.80
  4375.7 2165.89  4381.3 2164.80  4441.0 2162.50  4456.9 2163.12  4487.3 2161.70
  4568.5 2160.36  4741.1 2158.92  4933.9 2158.61  4972.5 2157.29  4972.8 2156.79
  4976.5 2157.29  5054.1 2157.69  5132.8 2159.18  5138.7 2158.73  5255.6 2162.24
  5408.8 2165.12  5421.5 2165.99  5466.4 2165.89  5480.8 2166.78  5493.5 2166.45
  5502.8 2167.30  5508.7 2166.71  5602.7 2169.33  5617.9 2170.49  5646.7 2170.81
#Mann=3,-1,0
  4145.8    0.07       0  4972.5    0.05       0  4976.5    0.07       0
Bank Sta=4972.5,4976.5
Exp/Cntr=0.3,0.1

Type RM Length L Ch R = 1,6986,448,448,448
BEGIN DESCRIPTION:
Stream0341 15.0
END DESCRIPTION:
XS GIS Cut Line= 3
      1822175.02     13970674.99      1822475.00     13970475.00
      1823074.99     13970425.00
#Sta/Elev= 30
  4640.0 2159.77  4751.8 2155.82  4863.8 2152.79  4941.9 2152.33  4964.5 2151.19
  4978.0 2149.57  4987.0 2149.22  4993.0 2150.88  4997.5 2149.64  5010.6 2149.26
  5050.7 2151.33  5058.2 2150.61  5063.2 2151.04  5070.8 2149.21  5088.8 2148.92
  5089.1 2148.42  5092.6 2148.42  5092.8 2148.92  5100.9 2150.31  5110.9 2151.09
  5141.0 2151.91  5151.1 2151.34  5178.6 2151.86  5183.7 2151.13  5211.3 2152.14
  5231.3 2150.99  5251.4 2153.12  5351.7 2153.70  5432.0 2157.11  5602.6 2162.32
#Mann=4,-1,0
  4640.0     0.1       0  4751.8    0.07       0  5088.8    0.05       0
  5092.8    0.07       0
Bank Sta=5088.8,5092.8
Exp/Cntr=0.3,0.1

Type RM Length L Ch R = 1,6538,445,445,445
BEGIN DESCRIPTION:
Stream0341 14.0
END DESCRIPTION:
XS GIS Cut Line= 3
      1822224.98     13970975.01      1822525.00     13970875.00
      1823324.96     13970575.02
#Sta/Elev= 30
  4675.2 2161.03  4759.5 2159.89  4808.2 2157.74  4865.0 2156.51  4893.5 2154.83
  4938.7 2152.95  4949.3 2151.72  4988.8 2148.74  4994.1 2148.74  4998.9 2146.48
  4999.2 2145.98  5003.2 2145.98  5003.6 2146.48  5006.6 2147.10  5012.8 2146.51
  5044.8 2146.96  5055.5 2147.59  5061.8 2148.50  5076.9 2148.17  5130.3 2149.93
  5141.0 2149.61  5172.1 2150.37  5257.6 2154.41  5318.1 2155.82  5333.2 2156.70
  5354.6 2156.59  5519.2 2158.91  5634.9 2162.21  5659.8 2163.45  5845.8 2168.37
#Mann=5,-1,0
  4675.2    0.07       0  4808.2     0.1       0  4893.5    0.07       0
  4998.9    0.05       0  5003.6    0.07       0
Bank Sta=4998.9,5003.6
Exp/Cntr=0.3,0.1

Type RM Length L Ch R = 1,6093,186,186,186
BEGIN DESCRIPTION:
Stream0341 13.0
END DESCRIPTION:
XS GIS Cut Line= 3
      1822325.04     13971275.00      1822675.00     13971275.00
      1823025.02     13970874.97
#Sta/Elev= 30
  4645.6 2159.77  4735.6 2157.48  4765.6 2156.01  4795.6 2153.43  4825.6 2152.25
  4885.6 2147.13  4905.6 2146.53  4959.3 2146.80  5006.0 2145.02  5014.5 2143.07
  5014.8 2142.57  5019.4 2143.07  5037.8 2145.18  5045.4 2145.37  5059.6 2144.56
  5101.9 2146.37  5151.7 2146.99  5194.4 2148.54  5215.3 2148.33  5221.9 2149.07
  5264.6 2150.02  5272.2 2149.39  5278.9 2150.22  5286.5 2149.87  5300.7 2150.62
  5356.7 2150.66  5407.0 2153.98  5456.4 2155.67  5519.9 2159.48  5527.1 2159.24
#Mann=5,-1,0
  4645.6    0.07       0  4959.3     0.1       0  5006.0    0.07       0
  5014.5    0.05       0  5019.4    0.07       0
Bank Sta=5014.5,5019.4
Exp/Cntr=0.3,0.1

Type RM Length L Ch R = 1,5907,141,141,141
BEGIN DESCRIPTION:
Mapping XS 3de716fd
END DESCRIPTION:
XS GIS Cut Line= 2
      1822214.67     13971420.37      1823239.47     13971420.50
#Sta/Elev= 30
  4439.2 2162.38  4569.5 2158.91  4589.5 2157.86  4609.5 2157.86  4639.5 2157.06
  4709.5 2153.00  4739.5 2151.99  4749.5 2151.00  4769.5 2148.07  4779.5 2148.22
  4799.5 2147.15  4859.5 2145.71  4939.5 2144.48  4959.5 2143.56  4979.5 2143.83
  4987.1 2142.38  4987.4 2141.88  4991.6 2141.88  4992.0 2142.38  4999.5 2142.51
  5019.5 2144.19  5129.5 2147.85  5169.5 2150.40  5209.5 2151.22  5299.5 2154.30
  5329.5 2155.97  5339.5 2156.08  5359.5 2157.86  5389.5 2159.16  5464.0 2160.68
#Mann=3,-1,0
  4439.2   0.035       0  4987.1   0.035       0  4992.0   0.035       0
Bank Sta=4987.1,4992
Exp/Cntr=0.3,0.1

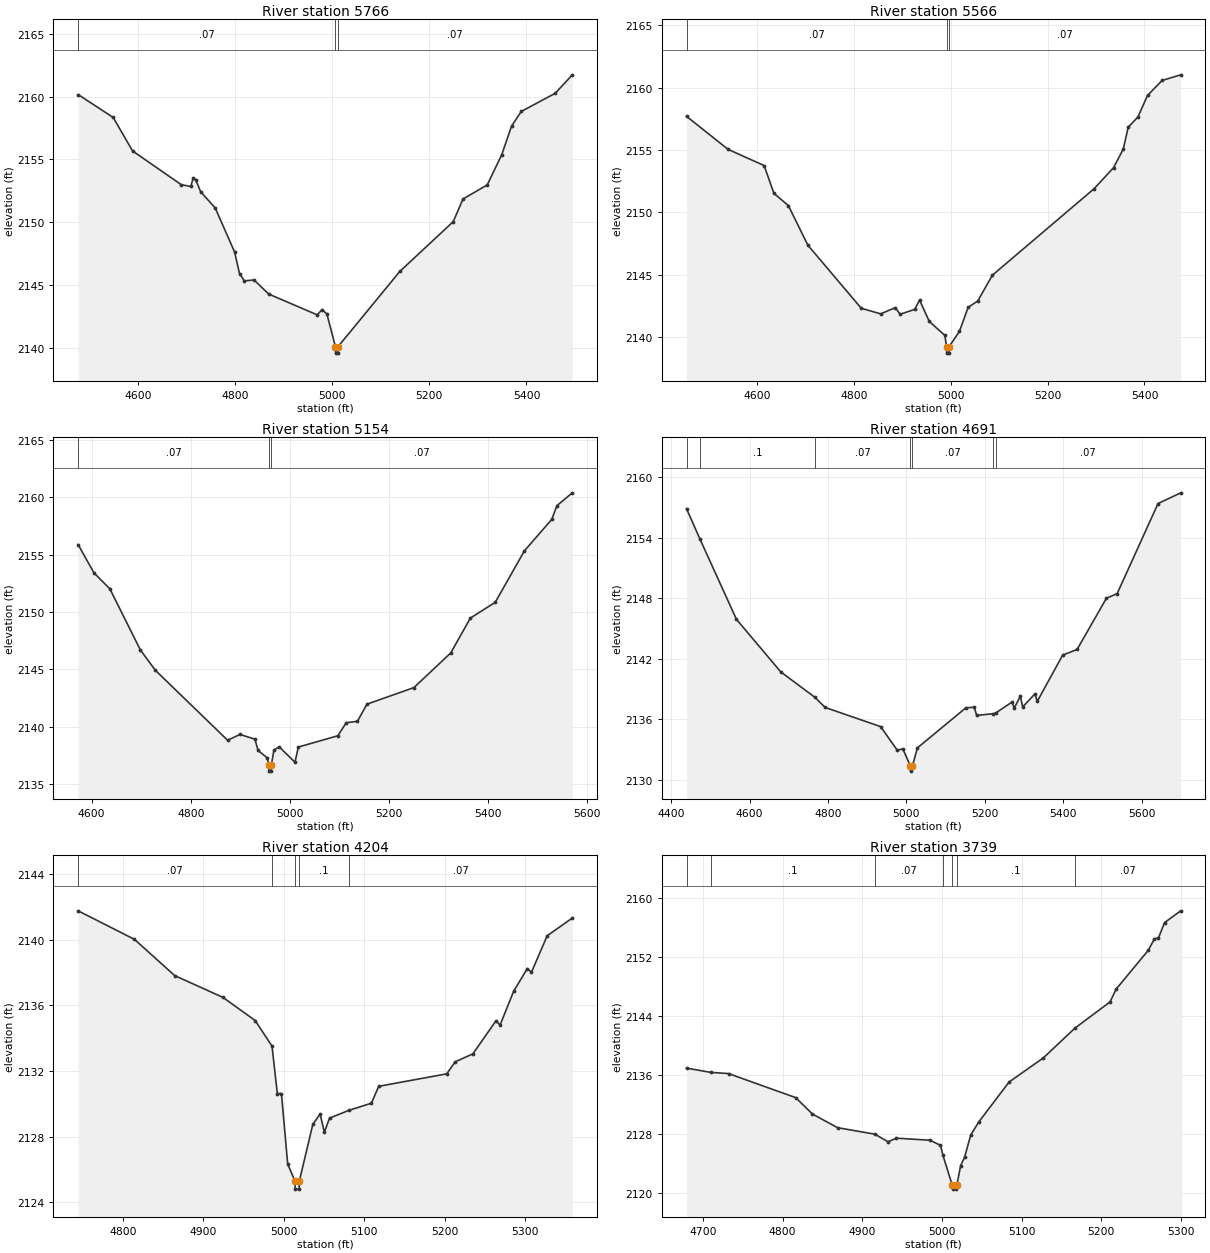
Type RM Length L Ch R = 1,5766,200,200,200
BEGIN DESCRIPTION:
Mapping XS 47f653f5
END DESCRIPTION:
XS GIS Cut Line= 2
      1822252.85     13971576.64      1823270.05     13971548.12
#Sta/Elev= 30
  4476.8 2160.17  4549.0 2158.34  4589.0 2155.67  4689.0 2152.99  4708.8 2152.84
  4713.8 2153.53  4719.0 2153.38  4729.0 2152.43  4759.1 2151.13  4799.1 2147.61
  4809.1 2145.90  4819.1 2145.32  4839.1 2145.39  4869.1 2144.27  4969.1 2142.61
  4979.1 2143.03  4989.1 2142.68  5006.7 2140.06  5007.1 2139.56  5011.3 2139.56
  5011.7 2140.06  5139.2 2146.07  5249.2 2150.04  5269.3 2151.84  5319.3 2152.97
  5349.3 2155.39  5369.3 2157.65  5389.3 2158.82  5459.3 2160.27  5494.4 2161.74
#Mann=3,-1,0
  4476.8    0.07       0  5006.7    0.05       0  5011.7    0.07       0
Bank Sta=5006.7,5011.7
Exp/Cntr=0.3,0.1

Type RM Length L Ch R = 1,5566,412,412,412
BEGIN DESCRIPTION:
Stream0341 12.0
END DESCRIPTION:
XS GIS Cut Line= 3
      1822265.19     13971704.16      1822806.03     13971740.79
      1823283.29     13971719.94
#Sta/Elev= 30
  4455.0 2157.71  4540.7 2155.06  4615.2 2153.76  4635.2 2151.54  4665.3 2150.54
  4705.4 2147.37  4815.6 2142.31  4855.7 2141.86  4885.8 2142.36  4895.8 2141.83
  4925.9 2142.22  4935.9 2142.97  4956.0 2141.25  4988.2 2140.13  4991.6 2139.21
  4992.0 2138.71  4996.2 2138.71  4996.6 2139.21  5018.2 2140.46  5036.1 2142.38
  5056.1 2142.90  5086.1 2144.96  5296.3 2151.91  5336.4 2153.60  5356.4 2155.09
  5366.4 2156.84  5386.4 2157.65  5406.4 2159.39  5436.5 2160.59  5474.8 2161.04
#Mann=3,-1,0
  4455.0    0.07       0  4991.6    0.05       0  4996.6    0.07       0
Bank Sta=4991.6,4996.6
Exp/Cntr=0.3,0.1

Type RM Length L Ch R = 1,5154,463,463,463
BEGIN DESCRIPTION:
Stream0341 11.0
END DESCRIPTION:
XS GIS Cut Line= 3
      1822324.98     13971974.99      1822725.00     13972125.00
      1823274.99     13971975.00
#Sta/Elev= 30
  4572.8 2155.87  4604.9 2153.40  4636.9 2152.01  4698.3 2146.70  4728.6 2144.92
  4874.5 2138.82  4899.5 2139.33  4929.7 2138.91  4935.9 2137.93  4954.6 2137.28
  4957.4 2136.63  4957.8 2136.13  4962.1 2136.13  4962.5 2136.63  4968.0 2137.97
  4978.7 2138.24  5010.4 2136.91  5017.3 2138.23  5096.8 2139.21  5114.0 2140.35
  5136.5 2140.47  5155.5 2141.96  5250.5 2143.41  5324.8 2146.43  5364.5 2149.47
  5414.6 2150.84  5473.4 2155.32  5528.7 2158.07  5539.0 2159.26  5570.1 2160.38
#Mann=3,-1,0
  4572.8    0.07       0  4957.4    0.05       0  4962.5    0.07       0
Bank Sta=4957.4,4962.5
Exp/Cntr=0.3,0.1

Type RM Length L Ch R = 1,4691,487,487,487
BEGIN DESCRIPTION:
Stream0341 10.0
END DESCRIPTION:
XS GIS Cut Line= 3
      1822274.98     13972174.98      1822675.00     13972575.00
      1823274.97     13972924.98
#Sta/Elev= 30
  4439.3 2156.90  4474.0 2153.84  4566.6 2145.91  4679.7 2140.69  4767.0 2138.16
  4792.9 2137.16  4934.3 2135.26  4976.7 2132.92  4990.9 2133.05  5010.3 2131.34
  5010.7 2130.84  5015.4 2131.34  5028.2 2133.15  5151.8 2137.13  5173.3 2137.18
  5179.1 2136.37  5221.8 2136.54  5227.4 2136.60  5269.2 2137.69  5275.0 2137.10
  5290.7 2138.28  5296.5 2137.21  5327.9 2138.51  5333.7 2137.76  5398.6 2142.36
  5435.4 2142.92  5509.9 2147.99  5537.6 2148.47  5641.7 2157.40  5699.6 2158.47
#Mann=7,-1,0
  4439.3    0.07       0  4474.0     0.1       0  4767.0    0.07       0
  5010.3    0.05       0  5015.4    0.07       0  5221.8     0.1       0
  5227.4    0.07       0
Bank Sta=5010.3,5015.4
Exp/Cntr=0.3,0.1

Type RM Length L Ch R = 1,4204,465,465,465
BEGIN DESCRIPTION:
Stream0341 9.0
END DESCRIPTION:
XS GIS Cut Line= 3
      1822325.00     13973025.00      1822575.00     13973025.00
      1822924.99     13973125.00
#Sta/Elev= 30
  4744.5 2141.77  4814.5 2140.03  4864.5 2137.82  4924.5 2136.49  4964.5 2135.08
  4985.4 2133.52  4992.0 2130.63  4997.1 2130.63  5004.9 2126.32  5013.9 2125.30
  5014.3 2124.80  5019.0 2124.80  5019.4 2125.30  5036.1 2128.75  5045.2 2129.38
  5050.4 2128.27  5056.9 2129.13  5080.7 2129.60  5108.9 2130.04  5118.0 2131.07
  5202.5 2131.83  5212.9 2132.56  5235.0 2133.05  5263.6 2135.06  5268.8 2134.81
  5285.7 2136.87  5302.6 2138.25  5307.8 2138.03  5327.3 2140.25  5358.5 2141.33
#Mann=5,-1,0
  4744.5    0.07       0  4985.4     0.1       0  5013.9    0.05       0
  5019.4     0.1       0  5080.7    0.07       0
Bank Sta=5013.9,5019.4
Exp/Cntr=0.3,0.1

Type RM Length L Ch R = 1,3739,445,445,445
BEGIN DESCRIPTION:
Stream0341 8.0
END DESCRIPTION:
XS GIS Cut Line= 3
      1822474.99     13973325.00      1822775.00     13973425.00
      1823075.02     13973375.00
#Sta/Elev= 30
  4679.4 2136.99  4710.0 2136.41  4732.1 2136.25  4816.4 2132.99  4837.5 2130.76
  4869.1 2128.91  4915.9 2128.03  4932.4 2127.00  4942.9 2127.49  4985.1 2127.21
  4998.2 2126.52  5001.3 2125.17  5013.1 2121.08  5013.6 2120.58  5018.3 2120.58
  5018.7 2121.08  5023.5 2123.75  5028.6 2124.95  5036.2 2127.92  5046.3 2129.69
  5084.3 2135.10  5127.4 2138.38  5167.0 2142.41  5211.1 2145.97  5218.7 2147.70
  5259.2 2152.98  5266.8 2154.52  5271.9 2154.65  5279.5 2156.72  5299.8 2158.32
#Mann=7,-1,0
  4679.4    0.07       0  4710.0     0.1       0  4915.9    0.07       0
  5001.3     0.1       0  5013.1    0.05       0  5018.7     0.1       0
  5167.0    0.07       0
Bank Sta=5013.1,5018.7
Exp/Cntr=0.3,0.1

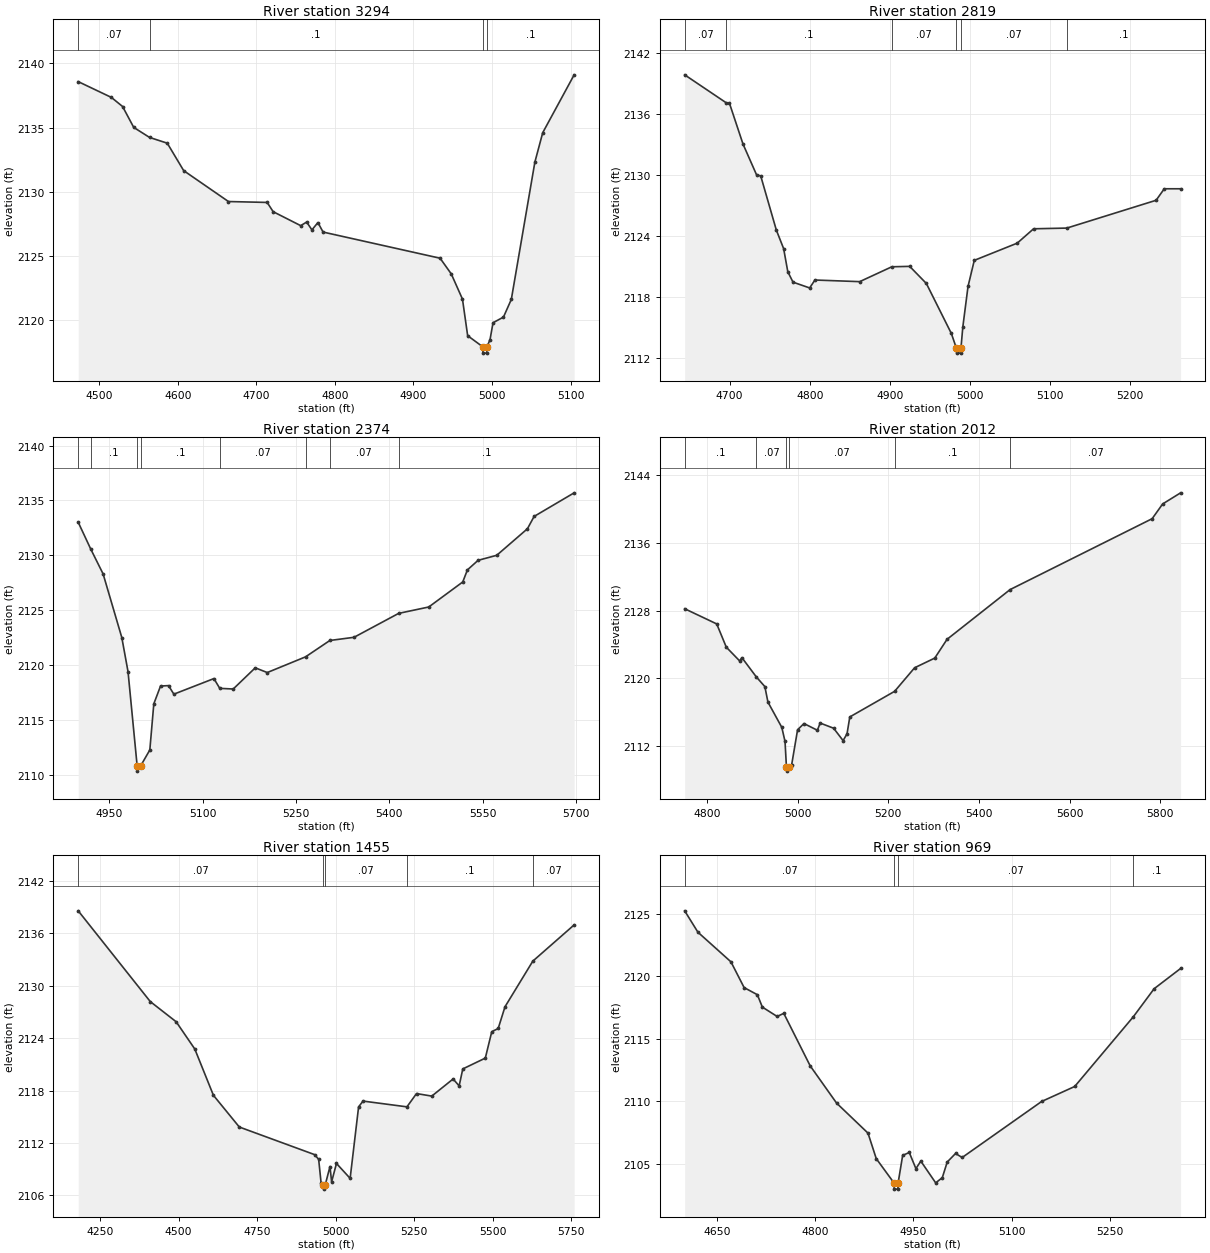
Type RM Length L Ch R = 1,3294,475,475,475
BEGIN DESCRIPTION:
Stream0341 7.0
END DESCRIPTION:
XS GIS Cut Line= 3
      1822324.99     13973474.99      1822725.00     13973825.00
      1822824.98     13973825.00
#Sta/Elev= 30
  4473.1 2138.58  4515.3 2137.35  4529.6 2136.64  4543.8 2135.01  4563.9 2134.23
  4586.5 2133.78  4607.4 2131.64  4664.4 2129.23  4713.7 2129.16  4721.3 2128.44
  4756.4 2127.35  4764.0 2127.63  4770.7 2127.02  4778.3 2127.59  4784.9 2126.85
  4933.9 2124.81  4948.1 2123.59  4962.4 2121.62  4969.0 2118.77  4988.1 2117.91
  4988.5 2117.41  4993.2 2117.41  4993.7 2117.91  4997.5 2118.47  5001.3 2119.78
  5014.6 2120.22  5024.6 2121.60  5054.6 2132.31  5064.6 2134.60  5104.6 2139.11
#Mann=4,-1,0
  4473.1    0.07       0  4563.9     0.1       0  4988.1    0.05       0
  4993.7     0.1       0
Bank Sta=4988.1,4993.7
Exp/Cntr=0.3,0.1

Type RM Length L Ch R = 1,2819,445,445,445
BEGIN DESCRIPTION:
Stream0341 6.0
END DESCRIPTION:
XS GIS Cut Line= 3
      1822025.03     13974025.01      1822375.00     13974125.00
      1822624.97     13974174.99
#Sta/Elev= 30
  4643.9 2139.84  4696.0 2137.08  4699.8 2137.04  4716.7 2133.04  4733.6 2130.02
  4738.8 2129.91  4758.3 2124.59  4767.4 2122.77  4772.6 2120.50  4779.1 2119.48
  4799.9 2118.91  4806.4 2119.69  4862.3 2119.53  4902.4 2120.99  4924.7 2121.03
  4945.5 2119.35  4976.7 2114.44  4982.9 2113.01  4983.3 2112.51  4988.2 2112.51
  4988.7 2113.01  4991.0 2115.08  4997.5 2119.06  5005.3 2121.62  5058.9 2123.31
  5079.3 2124.72  5120.8 2124.79  5232.2 2127.52  5242.4 2128.65  5262.8 2128.65
#Mann=6,-1,0
  4643.9    0.07       0  4696.0     0.1       0  4902.4    0.07       0
  4982.9    0.05       0  4988.7    0.07       0  5120.8     0.1       0
Bank Sta=4982.9,4988.7
Exp/Cntr=0.3,0.1

Type RM Length L Ch R = 1,2374,362,362,362
BEGIN DESCRIPTION:
Stream0341 5.0
END DESCRIPTION:
XS GIS Cut Line= 3
      1822024.99     13974425.00      1822125.00     13974425.00
      1822774.97     13974175.01
#Sta/Elev= 30
  4900.4 2133.01  4920.5 2130.57  4940.4 2128.30  4970.4 2122.51  4980.4 2119.40
  4995.0 2110.84  4995.5 2110.34  5000.9 2110.84  5015.4 2112.27  5021.8 2116.47
  5032.6 2118.09  5045.4 2118.13  5054.0 2117.35  5118.3 2118.77  5127.7 2117.88
  5149.3 2117.82  5184.7 2119.75  5204.0 2119.32  5265.5 2120.75  5304.5 2122.24
  5343.3 2122.53  5415.0 2124.71  5463.3 2125.29  5517.9 2127.57  5525.4 2128.67
  5542.5 2129.54  5572.5 2130.00  5621.8 2132.42  5632.5 2133.54  5696.8 2135.69
#Mann=8,-1,0
  4900.4    0.07       0  4920.5     0.1       0  4995.0    0.05       0
  5000.9     0.1       0  5127.7    0.07       0  5265.5     0.1       0
  5304.5    0.07       0  5415.0     0.1       0
Bank Sta=4995,5000.9
Exp/Cntr=0.3,0.1

Type RM Length L Ch R = 1,2012,557,557,557
BEGIN DESCRIPTION:
Stream0341 4.0
END DESCRIPTION:
XS GIS Cut Line= 3
      1822075.04     13974774.99      1822293.91     13974730.38
      1823007.48     13974231.22
#Sta/Elev= 30
  4750.6 2128.22  4821.3 2126.43  4842.4 2123.69  4871.8 2122.07  4876.9 2122.45
  4908.8 2120.17  4927.5 2119.04  4934.3 2117.21  4964.9 2114.23  4972.0 2112.57
  4975.1 2109.57  4975.6 2109.07  4981.0 2109.57  4986.7 2109.84  4999.7 2113.95
  5013.8 2114.68  5043.4 2113.89  5049.5 2114.74  5079.2 2114.13  5100.1 2112.67
  5108.8 2113.47  5114.9 2115.46  5213.8 2118.48  5257.9 2121.26  5302.4 2122.40
  5329.4 2124.61  5468.6 2130.48  5782.0 2138.84  5805.2 2140.58  5844.8 2141.89
#Mann=6,-1,0
  4750.6     0.1       0  4908.8    0.07       0  4975.1    0.05       0
  4981.0    0.07       0  5213.8     0.1       0  5468.6    0.07       0
Bank Sta=4975.1,4981
Exp/Cntr=0.3,0.1

Type RM Length L Ch R = 1,1455,486,486,486
BEGIN DESCRIPTION:
Stream0341 3.0
END DESCRIPTION:
XS GIS Cut Line= 3
      1821824.96     13975275.01      1822625.00     13975075.00
      1823361.08     13975238.62
#Sta/Elev= 30
  4180.3 2138.57  4409.7 2128.18  4492.1 2125.87  4551.4 2122.75  4610.7 2117.45
  4693.1 2113.82  4932.8 2110.66  4945.7 2110.12  4953.4 2107.43  4960.8 2107.21
  4961.2 2106.71  4966.7 2107.21  4981.8 2109.30  4986.9 2107.54  5002.4 2109.65
  5045.9 2107.94  5072.8 2116.12  5086.9 2116.79  5226.7 2116.13  5257.2 2117.65
  5305.8 2117.36  5373.7 2119.32  5392.9 2118.53  5404.5 2120.47  5476.2 2121.71
  5496.7 2124.73  5517.2 2125.10  5538.9 2127.59  5627.4 2132.81  5759.0 2136.96
#Mann=5,-1,0
  4180.3    0.07       0  4960.8    0.05       0  4966.7    0.07       0
  5226.7     0.1       0  5627.4    0.07       0
Bank Sta=4960.8,4966.7
Exp/Cntr=0.3,0.1

Type RM Length L Ch R = 1,969,454,454,454
BEGIN DESCRIPTION:
Stream0341 2.0
END DESCRIPTION:
XS GIS Cut Line= 3
      1822124.96     13975474.99      1822525.00     13975525.00
      1822874.99     13975475.00
#Sta/Elev= 30
  4600.9 2125.22  4621.1 2123.51  4671.5 2121.14  4691.6 2119.08  4711.8 2118.51
  4719.4 2117.52  4742.0 2116.77  4752.1 2117.02  4792.4 2112.82  4832.7 2109.84
  4880.6 2107.44  4893.2 2105.40  4920.2 2103.46  4920.7 2102.96  4926.1 2102.96
  4926.6 2103.46  4933.5 2105.66  4943.6 2105.89  4953.7 2104.60  4961.2 2105.20
  4983.9 2103.46  4994.0 2103.88  5001.5 2105.13  5014.2 2105.81  5024.3 2105.49
  5145.5 2109.97  5196.0 2111.17  5285.5 2116.75  5317.2 2118.99  5357.6 2120.61
#Mann=4,-1,0
  4600.9    0.07       0  4920.2    0.05       0  4926.6    0.07       0
  5285.5     0.1       0
Bank Sta=4920.2,4926.6
Exp/Cntr=0.3,0.1

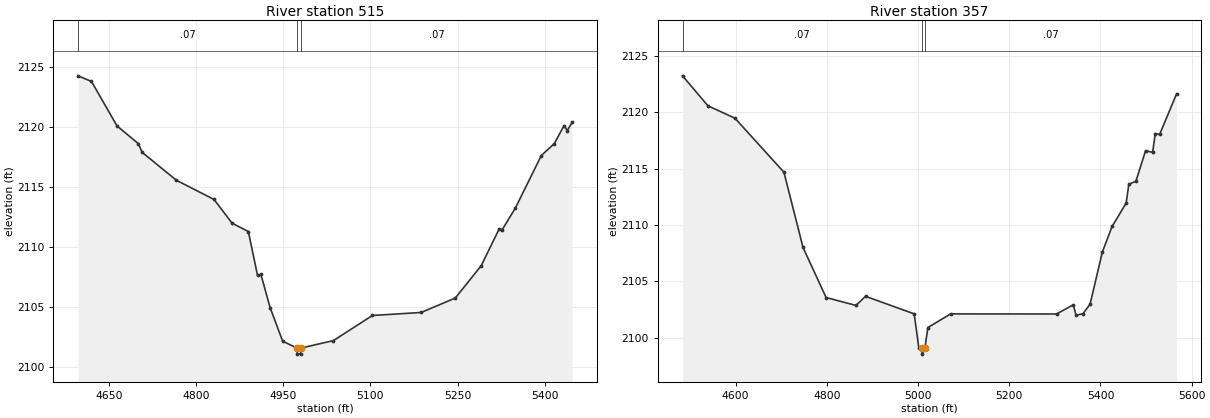
Type RM Length L Ch R = 1,515,158,158,158
BEGIN DESCRIPTION:
Stream0341 1.0
END DESCRIPTION:
XS GIS Cut Line= 3
      1822125.00     13975725.00      1822475.00     13975925.00
      1822874.97     13975725.01
#Sta/Elev= 30
  4596.9 2124.28  4619.9 2123.81  4663.8 2120.11  4700.6 2118.63  4707.0 2117.91
  4766.1 2115.58  4830.9 2113.98  4861.8 2112.01  4889.9 2111.31  4905.7 2107.65
  4911.5 2107.74  4927.3 2104.98  4948.9 2102.18  4973.7 2101.60  4974.2 2101.10
  4979.7 2101.10  4980.2 2101.60  5036.4 2102.23  5103.4 2104.32  5187.3 2104.57
  5246.0 2105.77  5290.7 2108.47  5321.5 2111.52  5327.0 2111.48  5349.4 2113.26
  5394.1 2117.64  5416.5 2118.64  5433.3 2120.14  5438.8 2119.72  5447.2 2120.41
#Mann=3,-1,0
  4596.9    0.07       0  4973.7    0.05       0  4980.2    0.07       0
Bank Sta=4973.7,4980.2
Exp/Cntr=0.3,0.1

Type RM Length L Ch R = 1,357,0,0,0
BEGIN DESCRIPTION:
Stream0341 0.0
END DESCRIPTION:
XS GIS Cut Line= 4
      1822039.19     13975851.83      1822370.96     13976082.47
      1822617.22     13976080.29      1822986.04     13975853.30
#Sta/Elev= 30
  4483.5 2123.23  4539.3 2120.57  4598.5 2119.47  4705.9 2114.68  4747.8 2108.00
  4798.4 2103.56  4863.9 2102.86  4884.8 2103.67  4991.6 2102.11  5001.6 2099.12
  5008.4 2099.04  5008.9 2098.54  5014.9 2099.04  5021.6 2100.90  5071.6 2102.11
  5303.8 2102.10  5340.5 2102.92  5346.4 2101.99  5361.8 2102.13  5377.2 2102.96
  5404.3 2107.61  5425.6 2109.87  5456.4 2111.94  5462.3 2113.62  5477.7 2113.87
  5499.0 2116.59  5514.4 2116.44  5520.3 2118.11  5529.8 2118.03  5566.9 2121.63
#Mann=3,-1,0
  4483.5    0.07       0  5008.4    0.05       0  5014.9    0.07       0
Bank Sta=5008.4,5014.9
Exp/Cntr=0.3,0.1

Chan Stop Cuts=-1