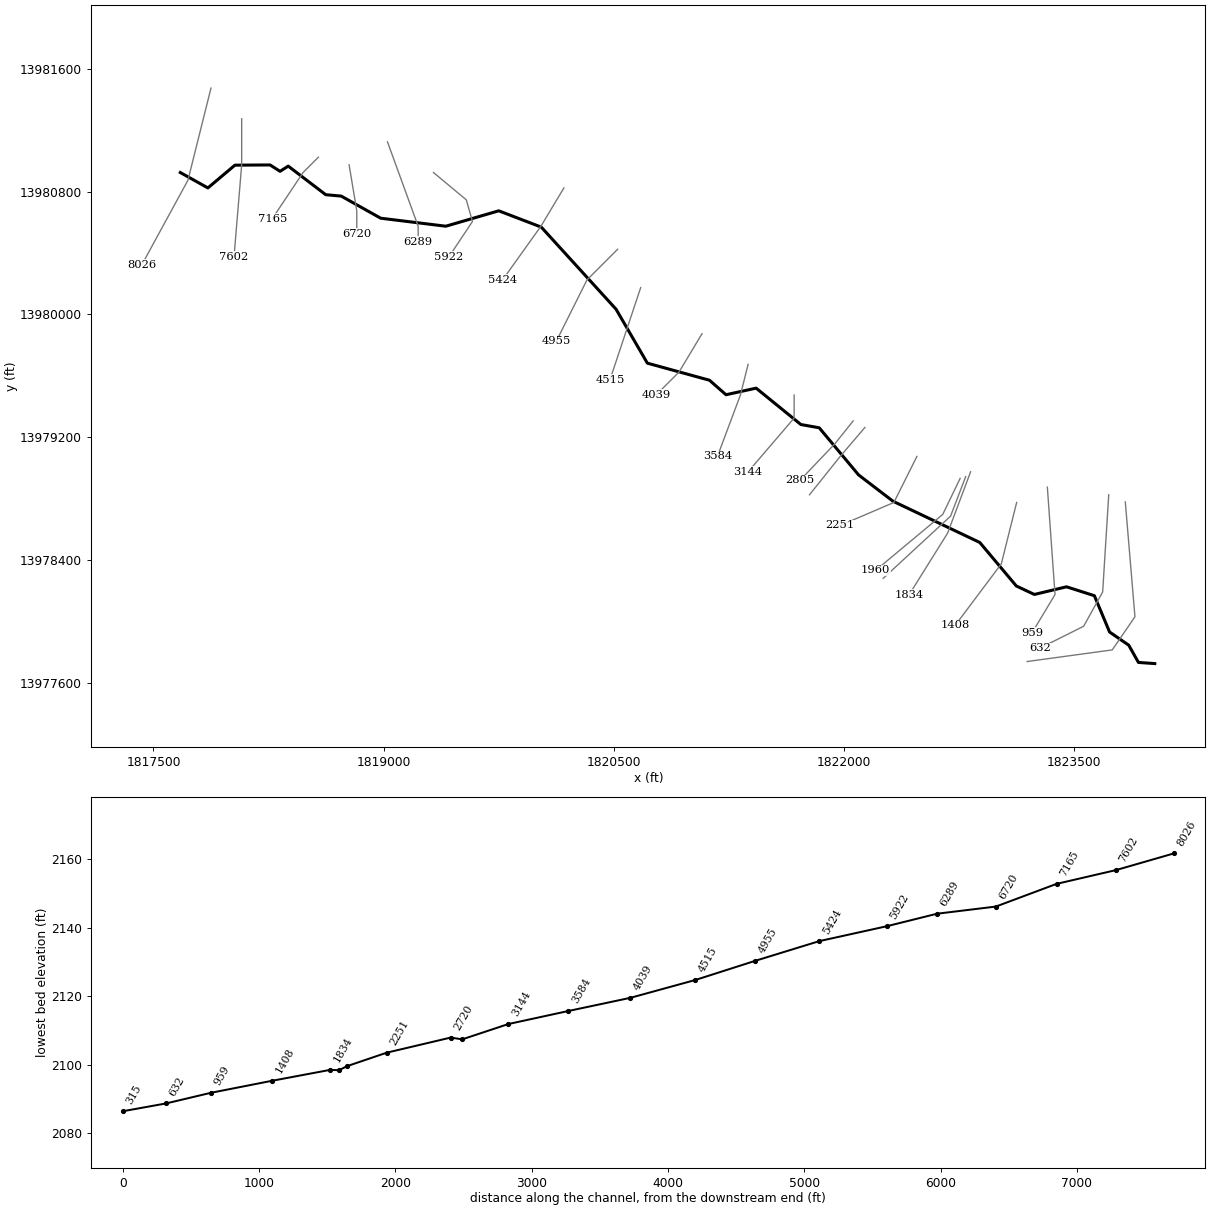
--- Stream0342.prj (project) ---

Proj Title=Stream0342 Base Level Engineering
Current Plan=p01
Default Exp/Contr=0.3,0.1
English Units
Geom File=g01
Flow File=f01
Plan File=p01
Y Axis Title=Elevation
X Axis Title(PF)=Main Channel Distance
X Axis Title(XS)=Station
BEGIN DESCRIPTION:
Stream0342
END DESCRIPTION:
DSS Export Rating Curves= 0
DSS Export Rating Curve Sorted= 0
DSS Export Volume Flow Curves= 0
DXF OffsetX= 0
DXF OffsetY= 0
DXF ScaleX= 1
DXF ScaleY= 10

--- Stream0342.p01 (plan) ---

Plan Title=Multiple Run
Short Identifier=Multiple
Geom File=g01
Flow File=f01
Subcritical Flow
K Sum by GR= 0
Std Step Tol= 0.01
Critical Tol= 0.01
Num of Std Step Trials= 20
Max Error Tol= 0.3
Flow Tol Ratio= 0.001
Split Flow NTrial= 30
Split Flow Tol= 0.02
Split Flow Ratio= 0.02
Log Output Level= 0
Friction Slope Method= 1
Unsteady Friction Slope Method= 2
Unsteady Bridges Friction Slope Method= 1
Parabolic Critical Depth
Global Vel Dist=  1 , 1 , 1
Global Log Level= 0
CheckData=True
Encroach Param= -1, 0, 0, 0
BEGIN DESCRIPTION:
Multiple Run
END DESCRIPTION:

--- Stream0342.f01 (steady flow) ---

Flow Title=Multiple
Program Version=4.10
Number of Profiles= 7
Profile Names=10-year,25-year,50-year,1pct_min,100-year,1pct_plu,500-year
River Rch & RM=Stream0342,Reach-1         ,8026
     860    1441    1984    1320    2633    5253    4583
River Rch & RM=Stream0342,Reach-1         ,5424
    1406    2421    3393    2294    4577    9133    8238
Boundary for River Rch & Prof#=Stream0342,Reach-1         , 1
Up Type= 0
Dn Type= 3
Dn Slope=0.008
Boundary for River Rch & Prof#=Stream0342,Reach-1         , 2
Up Type= 0
Dn Type= 3
Dn Slope=0.008
Boundary for River Rch & Prof#=Stream0342,Reach-1         , 3
Up Type= 0
Dn Type= 3
Dn Slope=0.008
Boundary for River Rch & Prof#=Stream0342,Reach-1         , 4
Up Type= 0
Dn Type= 3
Dn Slope=0.008
Boundary for River Rch & Prof#=Stream0342,Reach-1         , 5
Up Type= 0
Dn Type= 3
Dn Slope=0.008
Boundary for River Rch & Prof#=Stream0342,Reach-1         , 6
Up Type= 0
Dn Type= 3
Dn Slope=0.008
Boundary for River Rch & Prof#=Stream0342,Reach-1         , 7
Up Type= 0
Dn Type= 3
Dn Slope=0.008
DSS Import GetInterval= 0
DSS Import GetPeak= 0
DSS Import FillOption= 0

--- Stream0342.g01 (geometry) ---

Geom Title=Existing Conditions
Program Version=4.10

River Reach=Stream0342      ,Reach-1
Reach XY= 30
        1817675.       13980925.      1817854.87     13980824.59
      1818030.85     13980972.94      1818259.84     13980974.35
       1818325.1      13980932.8      1818378.23     13980966.76
      1818622.57     13980780.52       1818723.5     13980771.37
      1818980.94     13980627.26      1819404.97     13980575.07
       1819750.2     13980675.47       1820027.3     13980569.17
      1820514.24     13980034.68      1820718.55     13979682.74
       1821123.5     13979571.38      1821230.89     13979476.97
       1821427.3     13979519.91      1821718.84     13979282.88
      1821838.33     13979261.61      1822094.84     13978954.62
      1822318.94     13978783.14      1822884.68     13978514.24
      1823122.69     13978230.82      1823240.22     13978175.49
        1823450.      13978225.4       1823631.5     13978167.27
      1823730.59     13977930.61      1823855.22     13977845.12
      1823918.45      13977732.6        1824025.       13977725.

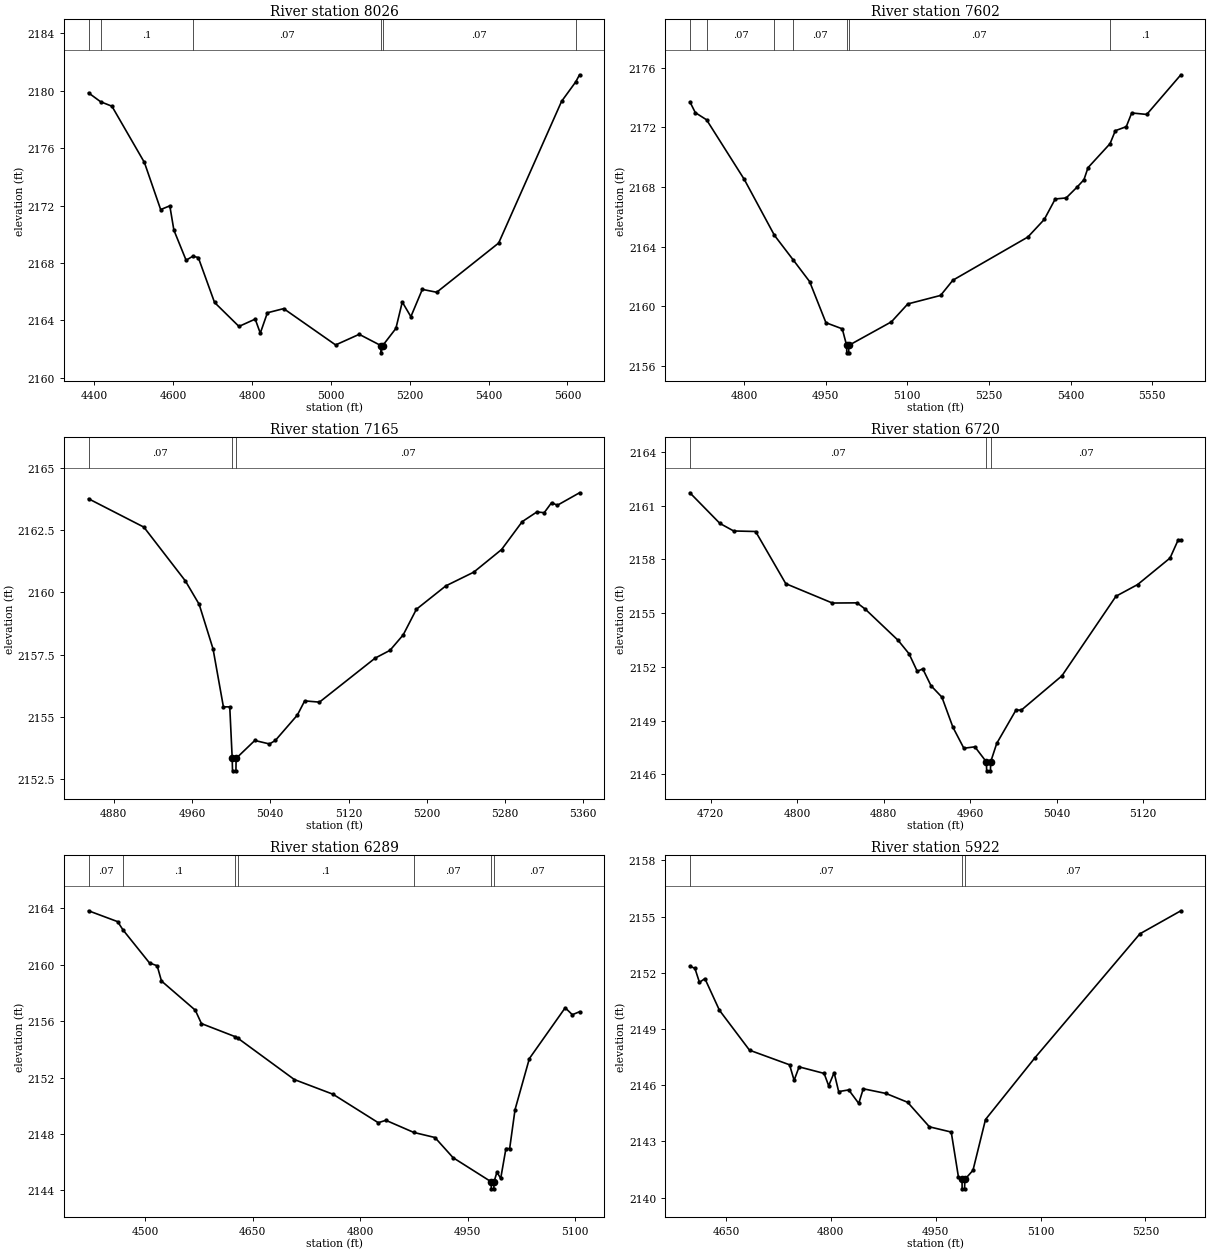
Type RM Length L Ch R = 1 ,8026    ,424,424,424
BEGIN DESCRIPTION:
Stream0342 18.0
END DESCRIPTION:
XS GIS Cut Line= 3
        1817875.     13981474.98        1817725.       13980875.
      1817425.02     13980325.04
#Sta/Elev= 30
  4385.8 2179.85  4416.5 2179.23  4445.1 2178.92  4527.5    2175  4568.7 2171.72
  4591.9 2171.98  4602.2 2170.29  4633.2 2168.19  4650.2 2168.47  4664.1 2168.38
  4705.3 2165.25  4767.2 2163.58  4808.4 2164.09  4821.3 2163.11  4839.3 2164.53
  4880.6 2164.82  5012.3 2162.29  5072.1 2163.03  5127.5 2162.24  5127.8 2161.74
  5131.5 2162.24  5165.1 2163.44  5181.3 2165.28  5203.1 2164.26  5232.1 2166.16
  5268.6 2165.96  5425.7 2169.39  5585.2 2179.26  5621.2 2180.62  5630.7 2181.11
#Mann= 6 ,-1 , 0
  4385.8     .07       0  4416.5      .1       0  4650.2     .07       0
  5127.5     .05       0  5131.5     .07       0  5621.2      .1       0
Bank Sta=5127.5,5131.5
XS Rating Curve= 0 ,0
Exp/Cntr=0.3,0.1

Type RM Length L Ch R = 1 ,7602    ,437,437,437
BEGIN DESCRIPTION:
Stream0342 17.0
END DESCRIPTION:
XS GIS Cut Line= 3
        1818075.     13981275.04        1818075.       13980975.
        1818025.     13980375.02
#Sta/Elev= 30
  4700.4 2173.71  4710.4 2172.98  4731.1  2172.5  4800.4  2168.5  4855.8 2164.75
  4889.7 2163.13  4920.4 2161.65  4950.4 2158.89  4980.4 2158.48  4988.4 2157.37
  4988.7 2156.87  4992.2 2156.87  4992.4 2157.37  5070.7 2158.95  5100.8 2160.15
    5161 2160.72  5183.6 2161.74  5321.5 2164.64  5351.6 2165.82  5371.7 2167.19
  5391.8 2167.26  5411.9 2167.99  5424.4 2168.48  5431.9 2169.29  5472.4  2170.9
  5482.1 2171.77  5502.2 2172.04  5512.2 2172.96  5539.8 2172.86  5602.5 2175.52
#Mann= 7 ,-1 , 0
  4700.4      .1       0  4731.1     .07       0  4855.8      .1       0
  4889.7     .07       0  4988.4     .05       0  4992.4     .07       0
  5472.4      .1       0
Bank Sta=4988.4,4992.4
XS Rating Curve= 0 ,0
Exp/Cntr=0.3,0.1

Type RM Length L Ch R = 1 ,7165    ,445,445,445
BEGIN DESCRIPTION:
Stream0342 16.0
END DESCRIPTION:
XS GIS Cut Line= 3
      1818574.99     13981024.99        1818475.       13980925.
      1818274.98     13980624.97
#Sta/Elev= 30
  4854.2 2163.76  4910.8 2162.62  4953.2 2160.46  4967.3 2159.52  4981.5 2157.73
  4992.1  2155.4  4998.6  2155.4  5001.1 2153.33  5001.4 2152.83  5004.9 2152.83
  5005.1 2153.33  5024.2 2154.05  5039.2 2153.91  5045.2 2154.05  5067.7 2155.07
  5075.2 2155.64  5090.3 2155.59  5147.3 2157.36  5162.4 2157.67  5175.9 2158.29
  5189.4 2159.32  5219.5 2160.26    5248 2160.81  5276.5 2161.72  5297.6 2162.84
  5312.6 2163.23  5320.1  2163.2  5327.6  2163.6  5333.6  2163.5  5356.2    2164
#Mann= 3 ,-1 , 0
  4854.2     .07       0  5001.1     .05       0  5005.1     .07       0
Bank Sta=5001.1,5005.1
XS Rating Curve= 0 ,0
Exp/Cntr=0.3,0.1

Type RM Length L Ch R = 1 ,6720    ,431,431,431
BEGIN DESCRIPTION:
Stream0342 15.0
END DESCRIPTION:
XS GIS Cut Line= 3
      1818775.01     13980974.97        1818825.       13980675.
        1818825.     13980525.01
#Sta/Elev= 30
  4700.7 2161.71  4728.5    2160  4741.2 2159.58  4761.5 2159.55  4789.4 2156.64
  4832.5 2155.56  4855.3 2155.57  4862.9 2155.22  4893.3 2153.48  4903.4 2152.73
    4911 2151.75  4916.1 2151.89  4923.7 2150.95  4933.8 2150.31    4944 2148.63
  4954.1 2147.46  4964.3 2147.54  4974.9  2146.7  4975.2  2146.2  4978.7  2146.2
  4978.9  2146.7  4984.5 2147.73  5002.3 2149.59  5007.3 2149.59  5044.8  2151.5
  5094.8 2155.94  5114.8 2156.59  5144.8 2158.07  5152.3 2159.08  5154.8 2159.08
#Mann= 3 ,-1 , 0
  4700.7     .07       0  4974.9     .05       0  4978.9     .07       0
Bank Sta=4974.9,4978.9
XS Rating Curve= 0 ,0
Exp/Cntr=0.3,0.1

Type RM Length L Ch R = 1 ,6289    ,367,367,367
BEGIN DESCRIPTION:
Stream0342 14.0
END DESCRIPTION:
XS GIS Cut Line= 3
      1819024.99     13981125.02        1819225.       13980575.
        1819225.     13980474.95
#Sta/Elev= 30
  4420.7 2163.83  4461.3 2163.06    4469 2162.46  4505.8 2160.13  4516.5 2159.93
  4522.5 2158.85  4569.7 2156.78  4578.3 2155.83    4625 2154.91  4628.7 2154.81
    4708 2151.86  4761.9 2150.82  4825.1  2148.8  4835.7 2148.97  4874.7 2148.11
  4904.2 2147.75  4929.5 2146.32  4982.7 2144.61  4982.9 2144.11  4986.4 2144.11
  4986.7 2144.61  4990.7 2145.29    4996 2144.85  5003.3 2146.97  5008.5 2146.97
    5016 2149.73    5036 2153.35    5086 2156.95    5096 2156.46    5106 2156.67
#Mann= 7 ,-1 , 0
  4420.7     .07       0    4469      .1       0    4625     .07       0
  4628.7      .1       0  4874.7     .07       0  4982.7     .05       0
  4986.7     .07       0
Bank Sta=4982.7,4986.7
XS Rating Curve= 0 ,0
Exp/Cntr=0.3,0.1

Type RM Length L Ch R = 1 ,5922    ,498,498,498
BEGIN DESCRIPTION:
Stream0342 13.0
END DESCRIPTION:
XS GIS Cut Line= 4
      1819324.99     13980925.01       1819538.8     13980746.83
      1819578.73      13980605.6      1819425.02     13980375.03
#Sta/Elev= 30
  4598.5 2152.35  4605.7 2152.24  4612.2 2151.49    4620 2151.69  4640.8    2150
  4683.8 2147.87  4741.1 2147.09  4747.6 2146.26  4754.7 2146.98  4790.5 2146.63
    4797 2145.97  4804.8 2146.67  4811.3 2145.66  4825.7 2145.75    4840 2145.03
  4846.5 2145.81    4879 2145.56  4909.9 2145.09  4941.1 2143.78  4972.3  2143.5
  4982.6  2141.1  4987.7 2140.97  4987.9 2140.47  4991.4 2140.47  4991.7 2140.97
  5003.4 2141.46  5021.3 2144.17  5091.9 2147.46  5242.1 2154.08  5300.7 2155.31
#Mann= 3 ,-1 , 0
  4598.5     .07       0  4987.7     .05       0  4991.7     .07       0
Bank Sta=4987.7,4991.7
XS Rating Curve= 0 ,0
Exp/Cntr=0.3,0.1

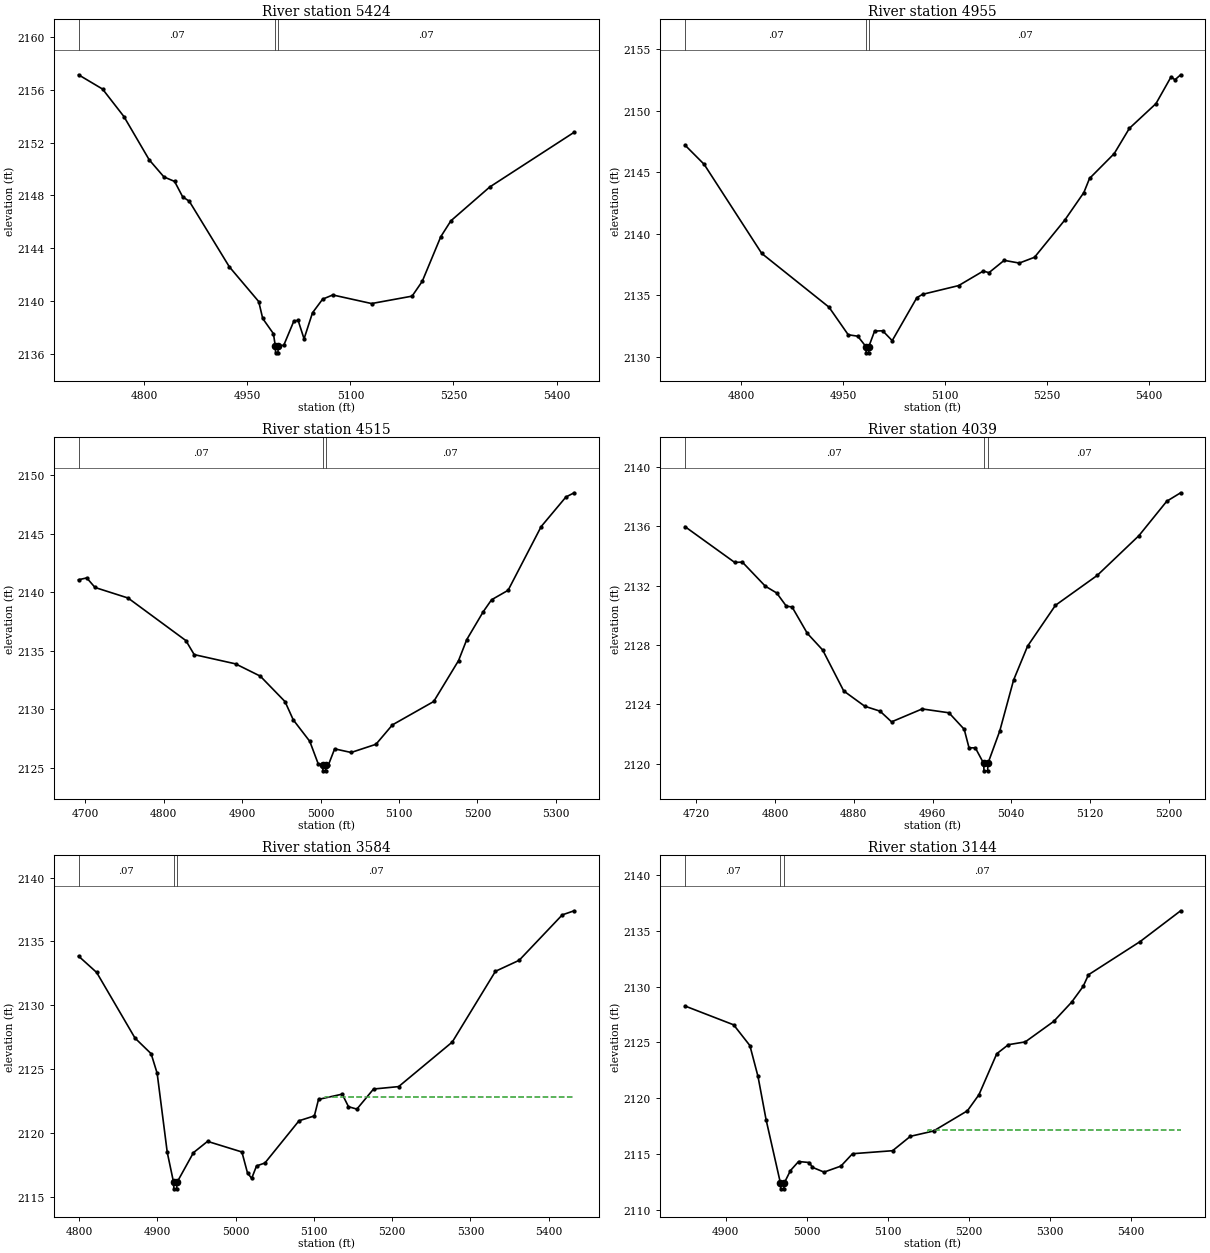
Type RM Length L Ch R = 1 ,5424    ,469,469,469
BEGIN DESCRIPTION:
Stream0342 12.0
END DESCRIPTION:
XS GIS Cut Line= 3
        1820175.     13980824.99        1820025.       13980575.
      1819774.98     13980224.97
#Sta/Elev= 30
    4704 2157.13    4739 2156.05  4770.1 2153.97    4807 2150.69  4828.4  2149.4
  4843.9 2149.06  4855.6  2147.9  4865.3 2147.56  4923.6  2142.6  4966.4 2139.97
  4972.2 2138.69  4987.8 2137.54  4990.6 2136.59  4990.9 2136.09  4994.4 2136.09
  4994.7 2136.59  5002.9 2136.67  5017.7 2138.51  5023.8 2138.54  5032.4 2137.15
  5044.7 2139.12  5059.4 2140.15  5074.2 2140.47  5130.7 2139.82  5189.7 2140.38
  5204.5  2141.5  5231.5 2144.88  5246.2 2146.08  5302.8 2148.64  5425.7 2152.78
#Mann= 3 ,-1 , 0
    4704     .07       0  4990.6     .05       0  4994.7     .07       0
Bank Sta=4990.6,4994.7
XS Rating Curve= 0 ,0
Exp/Cntr=0.3,0.1

Type RM Length L Ch R = 1 ,4955    ,440,440,440
BEGIN DESCRIPTION:
Stream0342 11.0
END DESCRIPTION:
XS GIS Cut Line= 3
      1820524.97     13980424.97        1820325.       13980225.
        1820125.     13979825.01
#Sta/Elev= 30
  4717.2 2147.21  4745.4 2145.65  4830.3 2138.41  4929.3 2134.05  4957.6 2131.81
  4971.7 2131.69  4983.8 2130.84  4984.1 2130.34  4987.7 2130.34  4987.9 2130.84
  4996.5 2132.11  5008.4 2132.13  5022.4 2131.33  5058.7 2134.82  5067.1 2135.09
  5120.2  2135.8  5156.5 2136.98  5164.9 2136.85  5187.3 2137.85  5209.6 2137.63
    5232  2138.1  5276.7 2141.13  5304.7 2143.36    5313  2144.5  5349.4 2146.52
  5371.7 2148.57  5410.9 2150.58  5433.2 2152.76  5438.8 2152.51  5447.2 2152.92
#Mann= 3 ,-1 , 0
  4717.2     .07       0  4983.8     .05       0  4987.9     .07       0
Bank Sta=4983.8,4987.9
XS Rating Curve= 0 ,0
Exp/Cntr=0.3,0.1

Type RM Length L Ch R = 1 ,4515    ,476,476,476
BEGIN DESCRIPTION:
Stream0342 10.0
END DESCRIPTION:
XS GIS Cut Line= 3
        1820675.     13980174.99        1820575.       13979875.
      1820475.01     13979575.04
#Sta/Elev= 30
  4691.1 2141.07  4701.6 2141.23  4712.2 2140.41  4754.3 2139.51  4828.1 2135.87
  4838.7 2134.67  4891.4 2133.88    4923 2132.83  4954.6 2130.65  4965.1 2129.09
  4986.2 2127.25  4996.8 2125.35  5002.6 2125.23  5002.8 2124.73  5006.5 2124.73
  5006.8 2125.23  5009.9 2125.23  5017.9 2126.61  5038.9  2126.3  5070.6    2127
  5091.6 2128.66  5144.3 2130.66    5176 2134.16  5186.5 2135.96  5207.6 2138.35
  5218.1 2139.36  5239.2 2140.17  5281.4 2145.62    5313 2148.15  5323.5 2148.51
#Mann= 3 ,-1 , 0
  4691.1     .07       0  5002.6     .05       0  5006.8     .07       0
Bank Sta=5002.6,5006.8
XS Rating Curve= 0 ,0
Exp/Cntr=0.3,0.1

Type RM Length L Ch R = 1 ,4039    ,455,455,455
BEGIN DESCRIPTION:
Stream0342 9.0
END DESCRIPTION:
XS GIS Cut Line= 3
      1821074.98     13979874.96        1820925.       13979625.
      1820775.02     13979475.02
#Sta/Elev= 30
  4708.5 2135.97    4759 2133.56  4766.8 2133.58  4790.1 2131.96  4801.7  2131.5
  4811.5 2130.61  4817.3 2130.56  4832.8 2128.78  4848.4 2127.66  4869.8  2124.9
  4891.2 2123.87  4906.7 2123.54  4918.4 2122.82  4949.5 2123.69  4976.7 2123.43
  4992.2 2122.32  4997.1 2121.07  5003.5 2121.07    5012 2120.02  5012.3 2119.52
    5016 2119.52  5016.3 2120.02  5028.3  2122.2  5042.4 2125.64  5056.6 2127.92
  5084.9 2130.67  5127.3 2132.68  5169.7 2135.36    5198 2137.68  5212.1 2138.25
#Mann= 3 ,-1 , 0
  4708.5     .07       0    5012     .05       0  5016.3     .07       0
Bank Sta=5012,5016.3
XS Rating Curve= 0 ,0
Exp/Cntr=0.3,0.1

Type RM Length L Ch R = 1 ,3584    ,440,440,440
BEGIN DESCRIPTION:
Stream0342 8.0
END DESCRIPTION:
XS GIS Cut Line= 3
        1821375.     13979675.01        1821325.       13979475.
      1821174.99     13979074.96
#Sta/Elev= 30
  4799.2 2133.86  4822.4 2132.58  4871.4 2127.45    4892 2126.23  4899.7  2124.7
  4912.6 2118.52  4920.7 2116.17    4921 2115.67  4924.7 2115.67    4925 2116.17
  4946.1  2118.5  4964.1 2119.38    5008 2118.55  5015.2  2116.9  5020.5 2116.49
  5026.7 2117.46  5037.4 2117.69    5081 2120.99  5100.6 2121.37  5105.9 2122.66
  5136.2 2123.07  5144.2 2122.09  5154.9  2121.9  5176.2 2123.47  5208.3 2123.66
  5276.8 2127.14    5332 2132.67  5362.3 2133.53  5417.4 2137.08  5432.6  2137.4
#Mann= 3 ,-1 , 0
  4799.2     .07       0  4920.7     .05       0    4925     .07       0
#XS Ineff= 2 , 0
                         5113.99         2122.88
Permanent Ineff=
       F       F
Bank Sta=4920.7,4925
XS Rating Curve= 0 ,0
Exp/Cntr=0.3,0.1

Type RM Length L Ch R = 1 ,3144    ,339,339,339
BEGIN DESCRIPTION:
Stream0342 7.0
END DESCRIPTION:
XS GIS Cut Line= 3
        1821675.     13979474.96        1821675.       13979325.
      1821375.02     13978975.02
#Sta/Elev= 30
    4850 2128.26    4910 2126.57    4930 2124.71    4940 2121.94    4950 2118.05
  4967.7 2112.36    4968 2111.86  4971.9 2111.86  4972.2 2112.36    4980  2113.5
    4990 2114.31  5003.2 2114.22  5007.1 2113.79  5021.4 2113.36  5042.2  2113.9
  5056.5 2115.01  5105.9 2115.28  5127.8 2116.57  5156.4 2117.05  5198.1 2118.86
  5212.3  2120.3  5234.3 2123.98  5248.6 2124.79  5269.4 2125.04  5304.5 2126.88
  5326.5  2128.6  5340.7 2130.01  5347.3 2131.06    5411 2134.04  5460.9  2136.8
#Mann= 3 ,-1 , 0
    4850     .07       0  4967.7     .05       0  4972.2     .07       0
#XS Ineff= 2 , 0
                         5148.95         2117.13
Permanent Ineff=
       F       F
Bank Sta=4967.7,4972.2
XS Rating Curve= 0 ,0
Exp/Cntr=0.3,0.1

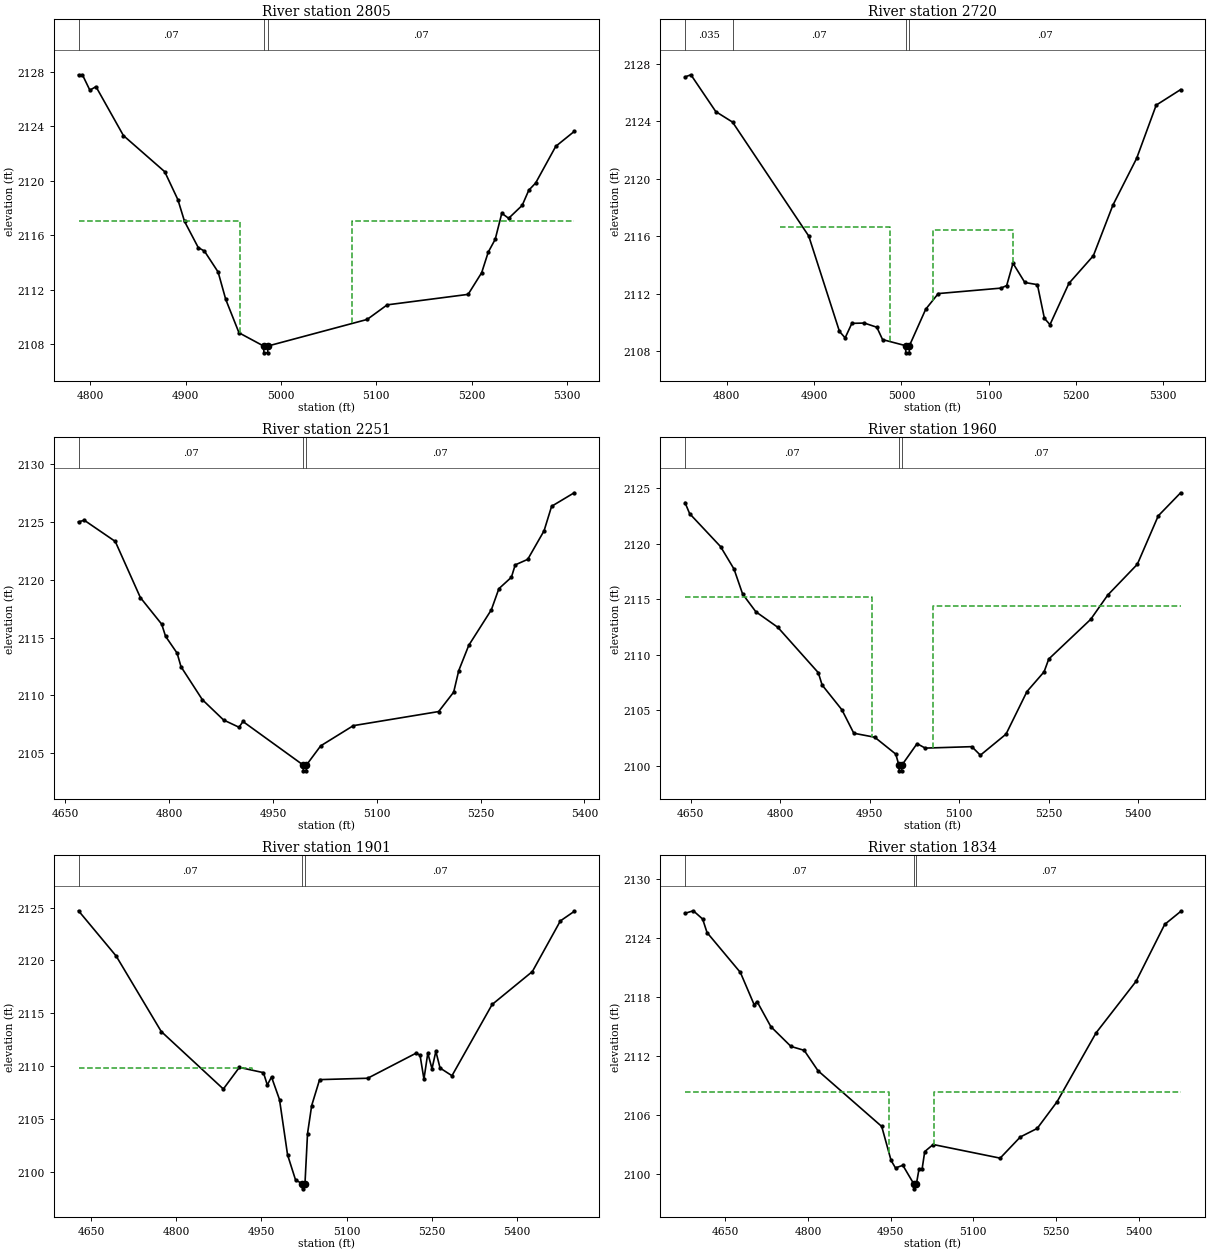
Type RM Length L Ch R = 1 ,2805    ,85,85,85
BEGIN DESCRIPTION:
Stream0342 6.2
END DESCRIPTION:
XS GIS Cut Line= 3
      1822059.79     13979306.39      1821941.34     13979158.38
      1821713.44      13978919.4
#Sta/Elev= 30
  4787.8 2127.78  4791.9 2127.78  4799.7 2126.65  4806.1 2126.91  4834.9 2123.32
  4878.2 2120.67    4892 2118.62    4899 2117.02  4913.4  2115.1  4919.8 2114.85
  4934.2 2113.31  4942.2  2111.3  4956.1 2108.85  4981.9 2107.88  4982.2 2107.38
  4986.1 2107.38  4986.4 2107.88  5090.5 2109.83  5111.5  2110.9  5196.4 2111.67
  5210.6 2113.26  5217.5 2114.77  5224.8 2115.71  5231.7 2117.62  5238.9 2117.25
  5253.1  2118.2    5260 2119.31  5267.2 2119.84  5288.3 2122.53  5307.6 2123.62
#Mann= 3 ,-1 , 0
  4787.8     .07       0  4981.9     .05       0  4986.4     .07       0
#XS Ineff= 2 ,-1
 4771.01 4957.362117.077 5074.82 5309.082117.079
Permanent Ineff=
       F       F
Bank Sta=4981.9,4986.4
XS Rating Curve= 0 ,0
Exp/Cntr=0.3,0.1

Type RM Length L Ch R = 1 ,2720    ,469,469,469
BEGIN DESCRIPTION:
Stream0342 6.0
END DESCRIPTION:
XS GIS Cut Line= 3
      1822135.88     13979263.43        1821975.       13979075.
      1821775.01     13978825.02
#Sta/Elev= 30
    4752 2127.07  4758.8 2127.22  4787.3 2124.66  4806.5 2123.93  4893.8 2116.01
    4929 2109.38  4935.5 2108.93  4943.2 2109.94  4957.5 2109.96  4971.8 2109.67
  4978.4 2108.81  5004.7 2108.39    5005 2107.89  5008.9 2107.89  5009.2 2108.39
  5027.8 2110.92  5042.2 2112.01  5114.2 2112.39  5120.6 2112.57  5127.8 2114.12
  5141.4 2112.78  5155.8 2112.63  5163.8 2110.29  5170.2 2109.85  5191.9 2112.72
  5219.9 2114.64  5242.3 2118.16  5269.5 2121.41  5291.9 2125.11  5319.9 2126.19
#Mann= 4 ,-1 , 0
    4752    .035       0  4806.5     .07       0  5004.7     .05       0
  5009.2     .07       0
#XS Ineff= 2 ,-1
 4860.83 4986.712116.622 5035.66 5127.972116.459
Permanent Ineff=
       F       F
Bank Sta=5004.7,5009.2
XS Rating Curve= 0 ,0
Exp/Cntr=0.3,0.1

Type RM Length L Ch R = 1 ,2251    ,291,291,291
BEGIN DESCRIPTION:
Stream0342 5.0
END DESCRIPTION:
XS GIS Cut Line= 3
        1822475.       13979075.        1822325.       13978775.
        1821975.       13978625.
#Sta/Elev= 30
  4668.9 2125.03  4677.3 2125.16    4722 2123.33  4758.3 2118.47  4789.1 2116.17
  4794.7 2115.12  4811.4 2113.66    4817 2112.49  4847.8 2109.64  4878.5 2107.88
  4900.9 2107.25  4906.5 2107.75  4993.6 2103.98  4993.9 2103.48  4997.9 2103.48
  4998.2 2103.98  5018.8 2105.64    5066 2107.39  5189.3 2108.61    5211 2110.29
  5218.3 2112.15  5232.8 2114.34  5265.4 2117.41  5276.3 2119.24  5294.4 2120.23
  5299.9  2121.3    5318 2121.78  5341.6 2124.25  5352.5 2126.37  5385.1 2127.54
#Mann= 3 ,-1 , 0
  4668.9     .07       0  4993.6     .05       0  4998.2     .07       0
Bank Sta=4993.6,4998.2
XS Rating Curve= 0 ,0
Exp/Cntr=0.3,0.1

Type RM Length L Ch R = 1 ,1960    ,59,59,59
BEGIN DESCRIPTION:
Mapping XS 3b4b6713
END DESCRIPTION:
XS GIS Cut Line= 3
      1822756.73       13978932.      1822643.48     13978697.28
       1822205.8     13978332.15
#Sta/Elev= 30
  4640.7 2123.73  4648.5 2122.73  4700.3 2119.76  4722.9 2117.73  4737.3 2115.48
  4759.5 2113.88  4796.3 2112.48  4864.1 2108.39  4870.5 2107.28  4903.6 2105.05
  4923.6 2102.93  4958.7 2102.57  4993.9 2101.05  4999.3 2100.04  4999.7 2099.54
  5003.7 2099.54    5004 2100.04  5029.6 2101.99  5043.3 2101.59  5121.4 2101.72
  5135.7 2100.95  5178.7 2102.85  5213.8 2106.69  5242.5 2108.47  5250.3 2109.62
  5320.6  2113.2  5349.2 2115.39  5398.7 2118.16  5433.8 2122.53  5471.3 2124.61
#Mann= 3 ,-1 , 0
  4640.7     .07       0  4999.3     .05       0    5004     .07       0
#XS Ineff= 2 , 0
         4954.65 2115.18 5056.54          2114.4
Permanent Ineff=
       F       F
Bank Sta=4999.3,5004
XS Rating Curve= 0 ,0
Exp/Cntr=0.3,0.1

Type RM Length L Ch R = 1 ,1901    ,67,67,67
BEGIN DESCRIPTION:
Mapping XS 0700d799
END DESCRIPTION:
XS GIS Cut Line= 3
      1822793.05     13978943.83      1822694.26     13978685.83
      1822255.48     13978280.37
#Sta/Elev= 30
  4627.6 2124.71    4694 2120.42  4773.4 2113.27  4882.9 2107.82  4911.1 2109.87
  4953.6 2109.37  4960.4  2108.2  4967.8 2108.96  4981.9 2106.82  4996.1 2101.58
  5010.3 2099.18  5022.1 2098.86  5022.5 2098.36  5026.8 2098.86  5031.3  2103.6
  5038.6 2106.25  5052.6 2108.71  5137.3 2108.84  5222.4 2111.21  5229.6 2111.03
  5236.5 2108.76  5243.3 2111.22  5250.7 2109.74  5257.5 2111.39  5264.9 2109.81
  5285.9 2109.08  5356.7 2115.83  5427.6 2118.95    5477 2123.75  5501.3 2124.65
#Mann= 3 ,-1 , 0
  4627.6     .07       0  5022.1     .05       0  5026.8     .07       0
#XS Ineff= 2 , 0
         4933.67 2109.79
Permanent Ineff=
       F       F
Bank Sta=5022.1,5026.8
XS Rating Curve= 0 ,0
Exp/Cntr=0.3,0.1

Type RM Length L Ch R = 1 ,1834    ,426,426,426
BEGIN DESCRIPTION:
Stream0342 4.0
END DESCRIPTION:
XS GIS Cut Line= 3
      1822824.98     13978974.96        1822675.       13978575.
      1822424.97     13978174.96
#Sta/Elev= 30
    4577 2126.53  4592.1 2126.79    4609 2125.95    4617 2124.57  4677.5  2120.5
  4702.4 2117.22  4707.8 2117.53  4732.7 2114.98  4769.2 2112.96  4793.2 2112.56
  4818.1 2110.49  4933.8  2104.8  4950.8 2101.33  4958.8 2100.57  4972.1 2100.84
    4992 2098.94  4992.4 2098.44  4996.7 2098.94  5001.5 2100.48  5007.1 2100.48
  5011.8 2102.24  5027.1 2102.96  5148.6 2101.57  5185.2 2103.73  5215.8  2104.6
  5251.8 2107.32  5322.5 2114.34  5395.1  2119.6    5447  2125.4  5475.9 2126.72
#Mann= 3 ,-1 , 0
    4577     .07       0    4992     .05       0  4996.7     .07       0
#XS Ineff= 2 , 0
         4947.29 2108.27 5028.17         2108.34
Permanent Ineff=
       F       F
Bank Sta=4992,4996.7
XS Rating Curve= 0 ,0
Exp/Cntr=0.3,0.1

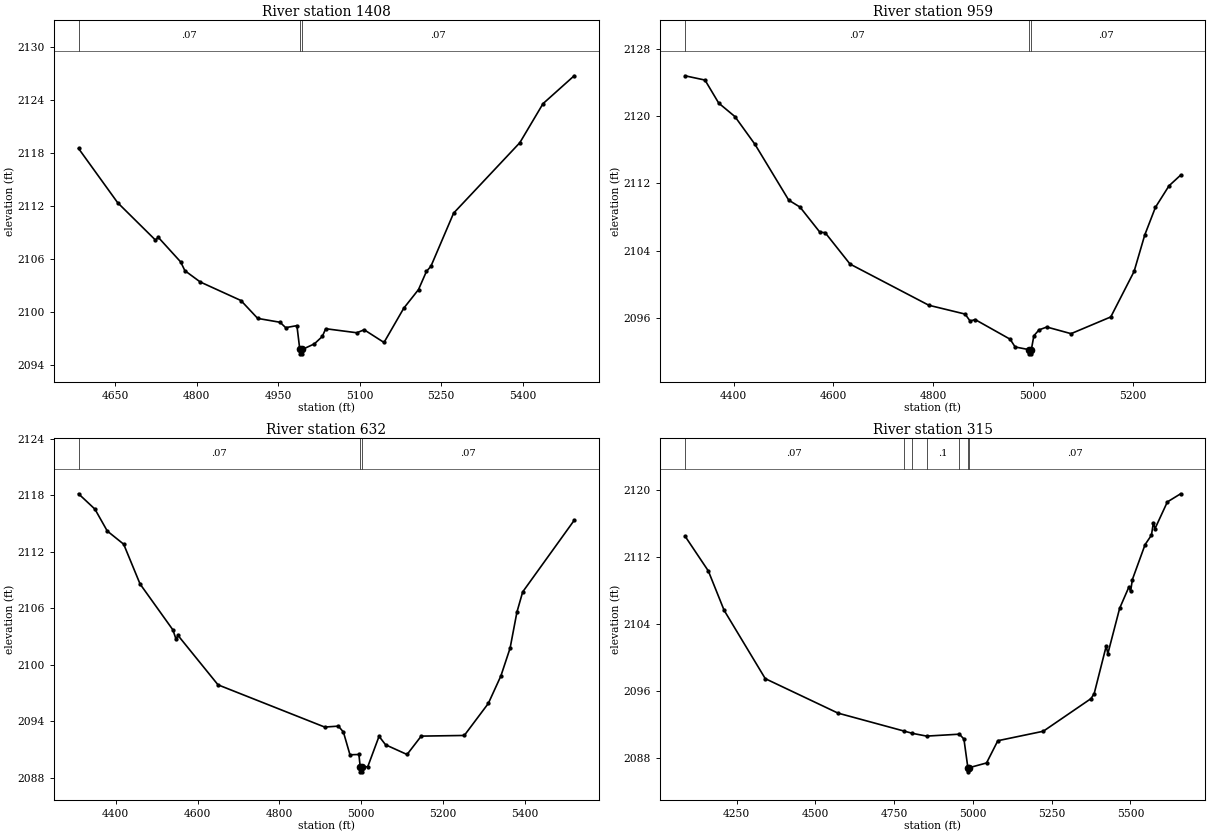
Type RM Length L Ch R = 1 ,1408    ,449,449,449
BEGIN DESCRIPTION:
Stream0342 3.0
END DESCRIPTION:
XS GIS Cut Line= 3
      1823124.99     13978774.95        1823025.       13978375.
      1822724.98     13977974.97
#Sta/Elev= 30
  4582.5 2118.55  4654.6 2112.39  4724.2 2108.15  4729.3 2108.47  4770.6 2105.67
  4778.3 2104.68  4806.6  2103.4  4881.4  2101.3  4912.3 2099.27  4953.5 2098.83
  4963.8 2098.22  4984.5 2098.45  4989.8 2095.75  4990.1 2095.25  4994.2 2095.25
  4994.5 2095.75  5016.6 2096.38  5031.2 2097.22  5037.5  2098.1  5094.8 2097.64
  5108.3 2097.98  5144.8 2096.54  5181.2 2100.43  5208.3 2102.54  5222.9  2104.6
  5231.2 2105.19  5272.9 2111.21  5394.8  2119.2  5437.5 2123.63  5494.8 2126.79
#Mann= 3 ,-1 , 0
  4582.5     .07       0  4989.8     .05       0  4994.5     .07       0
Bank Sta=4989.8,4994.5
XS Rating Curve= 0 ,0
Exp/Cntr=0.3,0.1

Type RM Length L Ch R = 1 ,959     ,327,327,327
BEGIN DESCRIPTION:
Stream0342 2.0
END DESCRIPTION:
XS GIS Cut Line= 3
        1823325.     13978874.96        1823375.       13978175.
      1823224.99     13977924.99
#Sta/Elev= 30
  4302.7 2124.81  4342.8  2124.3  4370.3 2121.56  4402.9 2119.95    4443 2116.65
  4510.7 2110.01  4533.2 2109.19  4573.3 2106.18  4583.4 2106.16  4633.5 2102.41
  4791.4 2097.51  4864.1 2096.46  4874.1 2095.63  4884.1 2095.81  4954.3 2093.47
  4964.3 2092.55    4992 2092.23  4992.4 2091.73  4996.5 2091.73  4996.8 2092.23
  5001.9 2093.88  5012.2 2094.58  5027.8 2094.92  5076.4 2094.13    5156 2096.12
  5202.7 2101.53  5224.1 2105.87  5245.5 2109.16  5272.7 2111.72    5296 2112.99
#Mann= 3 ,-1 , 0
  4302.7     .07       0    4992     .05       0  4996.8     .07       0
Bank Sta=4992,4996.8
XS Rating Curve= 0 ,0
Exp/Cntr=0.3,0.1

Type RM Length L Ch R = 1 ,632     ,317,317,317
BEGIN DESCRIPTION:
Stream0342 1.0
END DESCRIPTION:
XS GIS Cut Line= 4
        1823725.     13978825.05      1823685.42     13978191.66
      1823561.58     13977968.29      1823275.03     13977825.01
#Sta/Elev= 30
  4309.4 2118.14  4349.5 2116.51  4379.6 2114.19  4419.7 2112.79  4459.7 2108.57
  4539.9  2103.7  4547.4 2102.73  4552.4 2103.11  4650.1 2097.87  4910.6 2093.39
    4944 2093.49  4956.3 2092.86  4972.3 2090.45  4994.1 2090.48  4997.4 2089.14
  4997.7 2088.64  5001.8 2088.64  5002.2 2089.14  5015.8 2089.19  5043.3 2092.41
  5059.3 2091.51  5111.7 2090.48  5146.3 2092.43  5251.5  2092.5  5310.2  2095.9
  5340.9 2098.82  5363.3 2101.76  5380.1  2105.6  5394.1 2107.73  5519.8 2115.32
#Mann= 3 ,-1 , 0
  4309.4     .07       0  4997.4     .05       0  5002.2     .07       0
Bank Sta=4997.4,5002.2
XS Rating Curve= 0 ,0
Exp/Cntr=0.3,0.1

Type RM Length L Ch R = 1 ,315     ,0,0,0
BEGIN DESCRIPTION:
Stream0342 0.0
END DESCRIPTION:
XS GIS Cut Line= 4
      1823832.95     13978778.86      1823895.81     13978029.98
       1823747.8     13977814.18      1823193.25     13977738.45
#Sta/Elev= 30
  4086.4 2114.47  4160.5 2110.31  4210.7 2105.61  4341.2 2097.47    4572 2093.36
  4780.7 2091.23  4808.1 2090.95  4853.1 2090.62  4957.2 2090.85  4971.6 2090.27
  4984.1 2086.86  4984.5 2086.36  4988.9 2086.86  5043.4 2087.42  5079.2 2090.07
  5223.5  2091.2  5374.9 2095.09    5385 2095.69  5423.2 2101.36  5428.3 2100.44
  5465.8 2105.86  5495.5 2108.43  5500.6 2107.87  5506.1 2109.28  5546.5 2113.45
  5566.7 2114.58  5572.8 2116.07  5577.9 2115.35  5617.2 2118.54  5659.3 2119.51
#Mann= 7 ,-1 , 0
  4086.4     .07       0  4780.7      .1       0  4808.1     .07       0
  4853.1      .1       0  4957.2     .07       0  4984.1     .05       0
  4988.9     .07       0
Bank Sta=4984.1,4988.9
XS Rating Curve= 0 ,0
Exp/Cntr=0.3,0.1

Chan Stop Cuts=-1
Use User Specified Reach Order=0
Composite Channel Slope=5