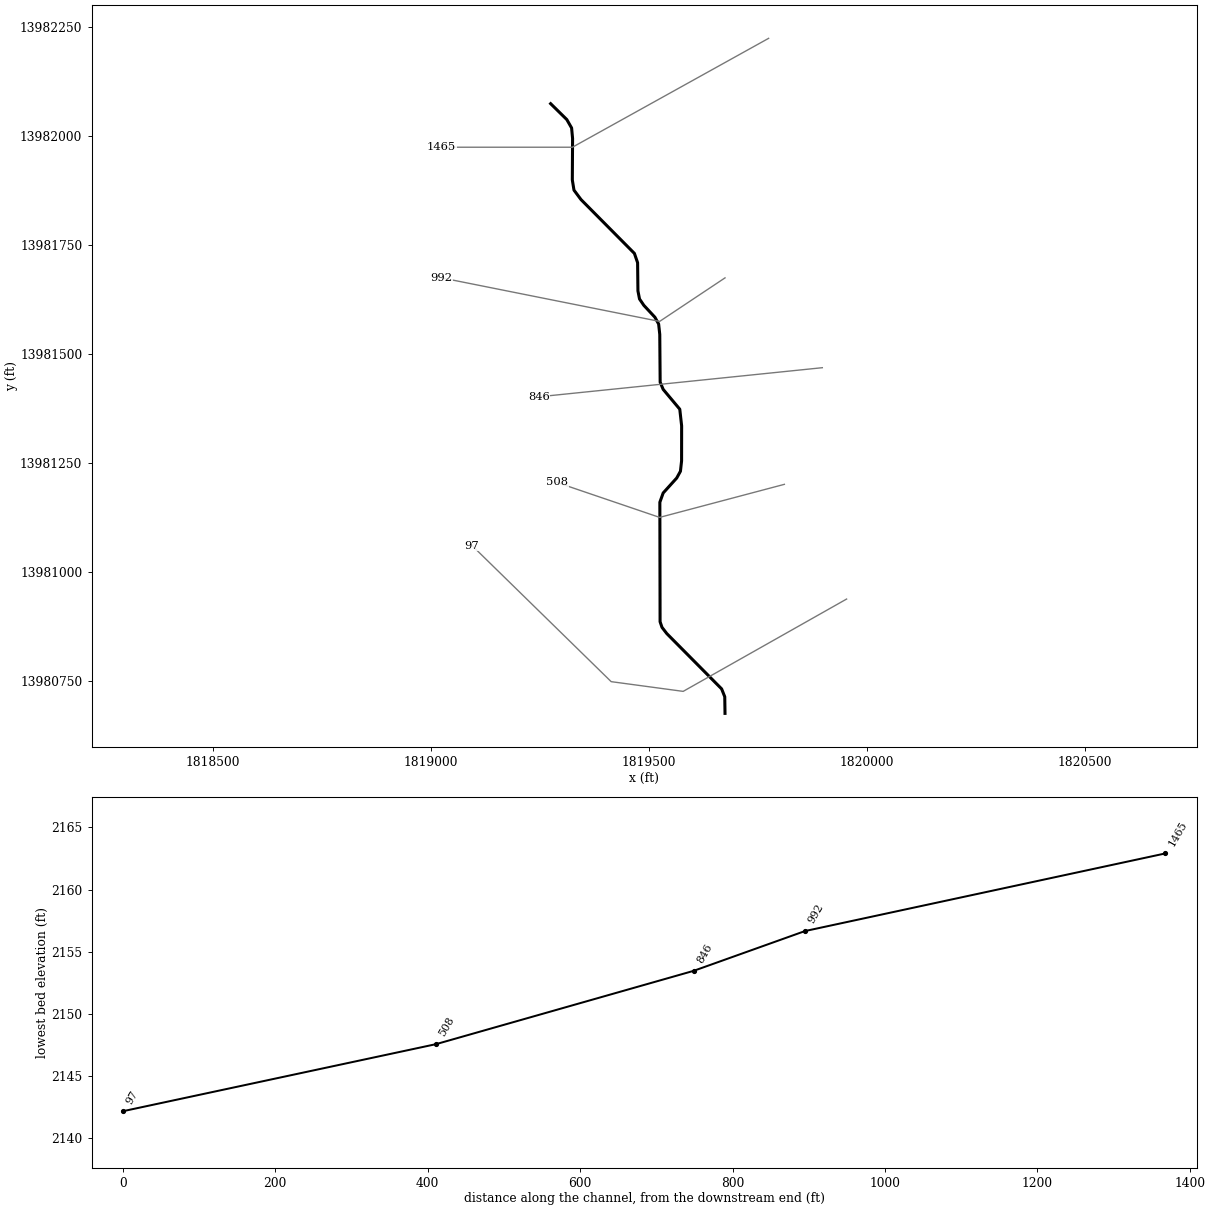
--- Stream0343.prj (project) ---

Proj Title=Stream0343 Base Level Engineering
Current Plan=p01
Default Exp/Contr=0.3,0.1
English Units
Geom File=g01
Flow File=f01
Plan File=p01
BEGIN DESCRIPTION:
Stream0343
END DESCRIPTION:

--- Stream0343.p01 (plan) ---

Plan Title=Multiple Run
Short Identifier=Multiple
Geom File=g01
Flow File=f01
Subcritical Flow
K Sum by GR= 0
Std Step Tol= 0.01
Critical Tol= 0.01
Num of Std Step Trials= 20
Max Error Tol= 0.3
Flow Tol Ratio= 0.001
Split Flow NTrial= 30
Split Flow Tol= 0.02
Split Flow Ratio= 0.02
Log Output Level= 0
Friction Slope Method= 1
Unsteady Friction Slope Method= 2
Unsteady Bridges Friction Slope Method= 1
Parabolic Critical Depth
Global Vel Dist=  1 , 1 , 1
Global Log Level= 0
CheckData=True
Encroach Param= -1, 0, 0, 0
BEGIN DESCRIPTION:
Multiple Run
END DESCRIPTION:

--- Stream0343.f01 (steady flow) ---

Flow Title=Multiple
Number of Profiles=7
Profile Names=10-year,25-year,50-year,1pct_min,100-year,1pct_plu,500-year
River Rch & RM= Stream0343,Reach-1,1465
     345     545     722     464     925    1847    1499
Boundary for River Rch & Prof#=Stream0343,Reach-1,1
Up Type=0
Dn Type=3
Dn Slope=0.005
Boundary for River Rch & Prof#=Stream0343,Reach-1,2
Up Type=0
Dn Type=3
Dn Slope=0.005
Boundary for River Rch & Prof#=Stream0343,Reach-1,3
Up Type=0
Dn Type=3
Dn Slope=0.005
Boundary for River Rch & Prof#=Stream0343,Reach-1,4
Up Type=0
Dn Type=3
Dn Slope=0.005
Boundary for River Rch & Prof#=Stream0343,Reach-1,5
Up Type=0
Dn Type=3
Dn Slope=0.005
Boundary for River Rch & Prof#=Stream0343,Reach-1,6
Up Type=0
Dn Type=3
Dn Slope=0.005
Boundary for River Rch & Prof#=Stream0343,Reach-1,7
Up Type=0
Dn Type=3
Dn Slope=0.005

--- Stream0343.g01 (geometry) ---

Geom Title=Existing Conditions

River Reach=Stream0343,Reach-1
Reach XY= 30
      1819275.00     13982075.00      1819312.08     13982038.50
      1819323.09     13982019.21      1819325.32     13981995.13
      1819324.72     13981899.88      1819328.54     13981876.47
      1819344.61     13981854.84      1819467.14     13981731.17
      1819474.48     13981709.78      1819475.25     13981645.10
      1819478.86     13981626.60      1819488.83     13981611.87
      1819514.15     13981584.65      1819522.73     13981569.06
      1819525.32     13981545.13      1819526.23     13981435.51
      1819533.15     13981418.95      1819571.23     13981373.43
      1819575.50     13981335.17      1819575.39     13981254.87
      1819572.75     13981230.94      1819564.15     13981215.36
      1819533.14     13981181.06      1819525.52     13981159.78
      1819526.05     13980885.43      1819530.46     13980872.55
      1819541.43     13980858.23      1819667.24     13980731.21
      1819674.41     13980713.16      1819675.00     13980675.00

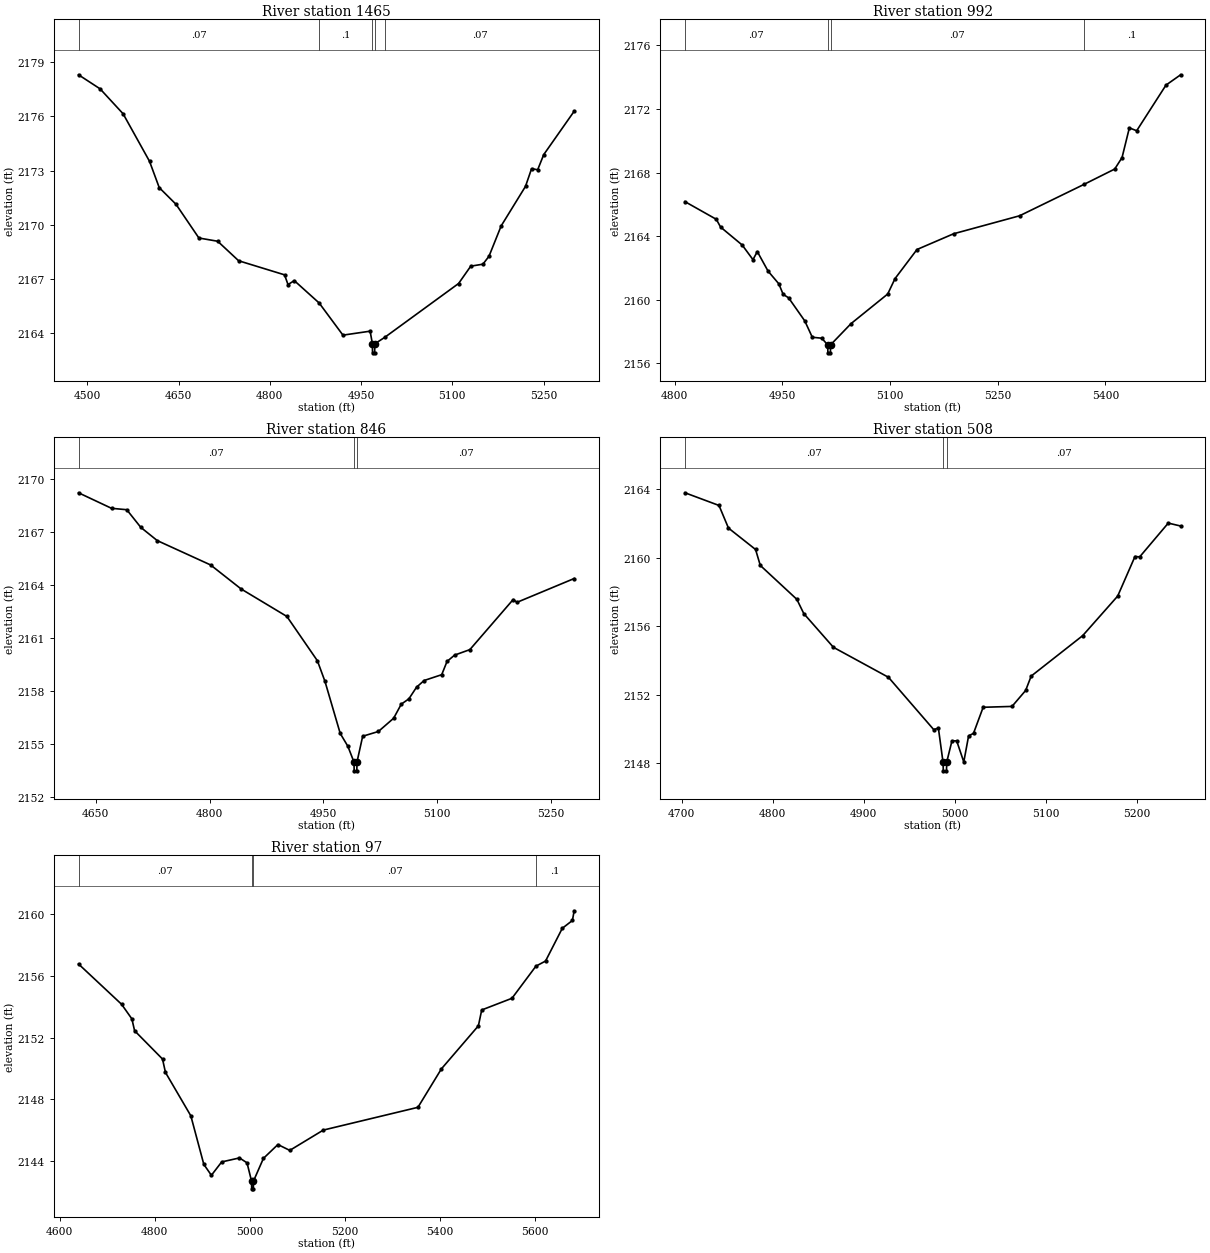
Type RM Length L Ch R = 1,1465,473,473,473
BEGIN DESCRIPTION:
Stream0343 3.0
END DESCRIPTION:
XS GIS Cut Line= 3
      1819775.04     13982225.02      1819325.00     13981975.00
      1819025.02     13981975.00
#Sta/Elev= 30
  4485.5 2178.31  4521.0 2177.53  4558.8 2176.15  4602.2 2173.52  4618.2 2172.06
  4645.7 2171.14  4683.4 2169.27  4714.3 2169.09  4748.7 2168.01  4824.2 2167.23
  4829.9 2166.69  4840.2 2166.91  4881.1 2165.67  4920.2 2163.89  4964.9 2164.11
  4968.6 2163.41  4968.8 2162.91  4972.3 2162.91  4972.6 2163.41  4989.0 2163.77
  5110.3 2166.75  5130.3 2167.71  5150.3 2167.82  5160.3 2168.26  5180.3 2169.94
  5220.3 2172.13  5230.3 2173.11  5240.3 2173.05  5250.3 2173.89  5300.3 2176.29
#Mann=5,-1,0
  4485.5    0.07       0  4881.1     0.1       0  4968.6    0.05       0
  4972.6     0.1       0  4989.0    0.07       0
Bank Sta=4968.6,4972.6
Exp/Cntr=0.3,0.1

Type RM Length L Ch R = 1,992,146,146,146
BEGIN DESCRIPTION:
Stream0343 2.0
END DESCRIPTION:
XS GIS Cut Line= 3
      1819675.03     13981675.02      1819525.00     13981575.00
      1819025.01     13981675.00
#Sta/Elev= 30
  4814.5 2166.17  4858.1 2165.06  4864.1 2164.57  4894.2 2163.44  4909.2 2162.52
  4915.2 2163.03  4930.2 2161.80  4945.2 2161.00  4951.2 2160.34  4958.8 2160.12
  4981.3 2158.67  4991.8 2157.64  5005.0 2157.58  5013.2 2157.16  5013.5 2156.66
  5017.0 2156.66  5017.2 2157.16  5045.8 2158.50  5096.8 2160.36  5107.0 2161.33
  5137.6 2163.16  5188.6 2164.15  5280.4 2165.28  5369.9 2167.25  5412.9 2168.22
  5423.1 2168.94  5433.3 2170.81  5443.5 2170.63  5484.3 2173.50  5504.7 2174.15
#Mann=4,-1,0
  4814.5    0.07       0  5013.2    0.05       0  5017.2    0.07       0
  5369.9     0.1       0
Bank Sta=5013.2,5017.2
Exp/Cntr=0.3,0.1

Type RM Length L Ch R = 1,846,338,338,338
BEGIN DESCRIPTION:
Stream0343 4.0
END DESCRIPTION:
XS GIS Cut Line= 2
      1819898.22     13981468.74      1819248.25     13981401.96
#Sta/Elev= 30
  4627.2 2169.22  4670.7 2168.34  4690.8 2168.26  4709.3 2167.26  4731.0 2166.51
  4801.3 2165.13  4841.5 2163.77  4901.9 2162.21  4942.1 2159.70  4952.1 2158.53
  4972.2 2155.58  4982.3 2154.85  4990.3 2153.96  4990.6 2153.46  4994.1 2153.46
  4994.3 2153.96  5001.8 2155.42  5022.5 2155.69  5042.6 2156.44  5052.7 2157.24
  5062.7 2157.54  5072.8 2158.20  5082.8 2158.58  5106.0 2158.91  5113.0 2159.66
  5123.0 2160.02  5143.1 2160.33  5200.2 2163.17  5205.2 2163.01  5280.6 2164.36
#Mann=3,-1,0
  4627.2    0.07       0  4990.3    0.05       0  4994.3    0.07       0
Bank Sta=4990.3,4994.3
Exp/Cntr=0.3,0.1

Type RM Length L Ch R = 1,508,411,411,411
BEGIN DESCRIPTION:
Stream0343 1.0
END DESCRIPTION:
XS GIS Cut Line= 3
      1819811.19     13981200.92      1819525.00     13981125.00
      1819289.47     13981205.18
#Sta/Elev= 30
  4703.5 2163.79  4740.9 2163.05  4751.3 2161.73  4781.1 2160.48  4786.3 2159.55
  4826.5 2157.57  4834.1 2156.74  4866.7 2154.77  4927.2 2153.02  4976.9 2149.97
  4982.1 2150.05  4987.2 2148.06  4987.5 2147.56  4991.0 2147.56  4991.2 2148.06
  4997.0 2149.31  5002.2 2149.31  5010.0 2148.08  5015.3 2149.60  5020.7 2149.75
  5031.3 2151.27  5063.0 2151.32  5078.0 2152.25  5084.1 2153.09  5140.7 2155.45
  5179.2 2157.76  5198.2 2160.07  5203.4 2160.05  5234.8 2162.02  5248.4 2161.85
#Mann=3,-1,0
  4703.5    0.07       0  4987.2    0.05       0  4991.2    0.07       0
Bank Sta=4987.2,4991.2
Exp/Cntr=0.3,0.1

Type RM Length L Ch R = 1,97,0,0,0
BEGIN DESCRIPTION:
Stream0343 0.0
END DESCRIPTION:
XS GIS Cut Line= 4
      1819953.95     13980937.53      1819579.03     13980725.52
      1819413.87     13980747.84      1819094.87     13981060.15
#Sta/Elev= 30
  4639.6 2156.78  4730.3 2154.16  4752.0 2153.21  4757.7 2152.44  4816.5 2150.60
  4822.7 2149.73  4876.1 2146.91  4903.5 2143.75  4919.4 2143.04  4941.1 2143.91
  4978.6 2144.17  4994.5 2143.85  5004.0 2142.66  5004.3 2142.16  5007.8 2142.16
  5008.0 2142.66  5029.0 2144.14  5059.5 2145.04  5084.5 2144.66  5155.1 2145.98
  5354.4 2147.46  5403.8 2149.96  5481.7 2152.76  5488.7 2153.79  5552.4 2154.55
  5602.9 2156.64  5623.1 2156.97  5658.4 2159.10  5679.7 2159.61  5683.4 2160.24
#Mann=4,-1,0
  4639.6    0.07       0  5004.0    0.05       0  5008.0    0.07       0
  5602.9     0.1       0
Bank Sta=5004,5008
Exp/Cntr=0.3,0.1

Chan Stop Cuts=-1