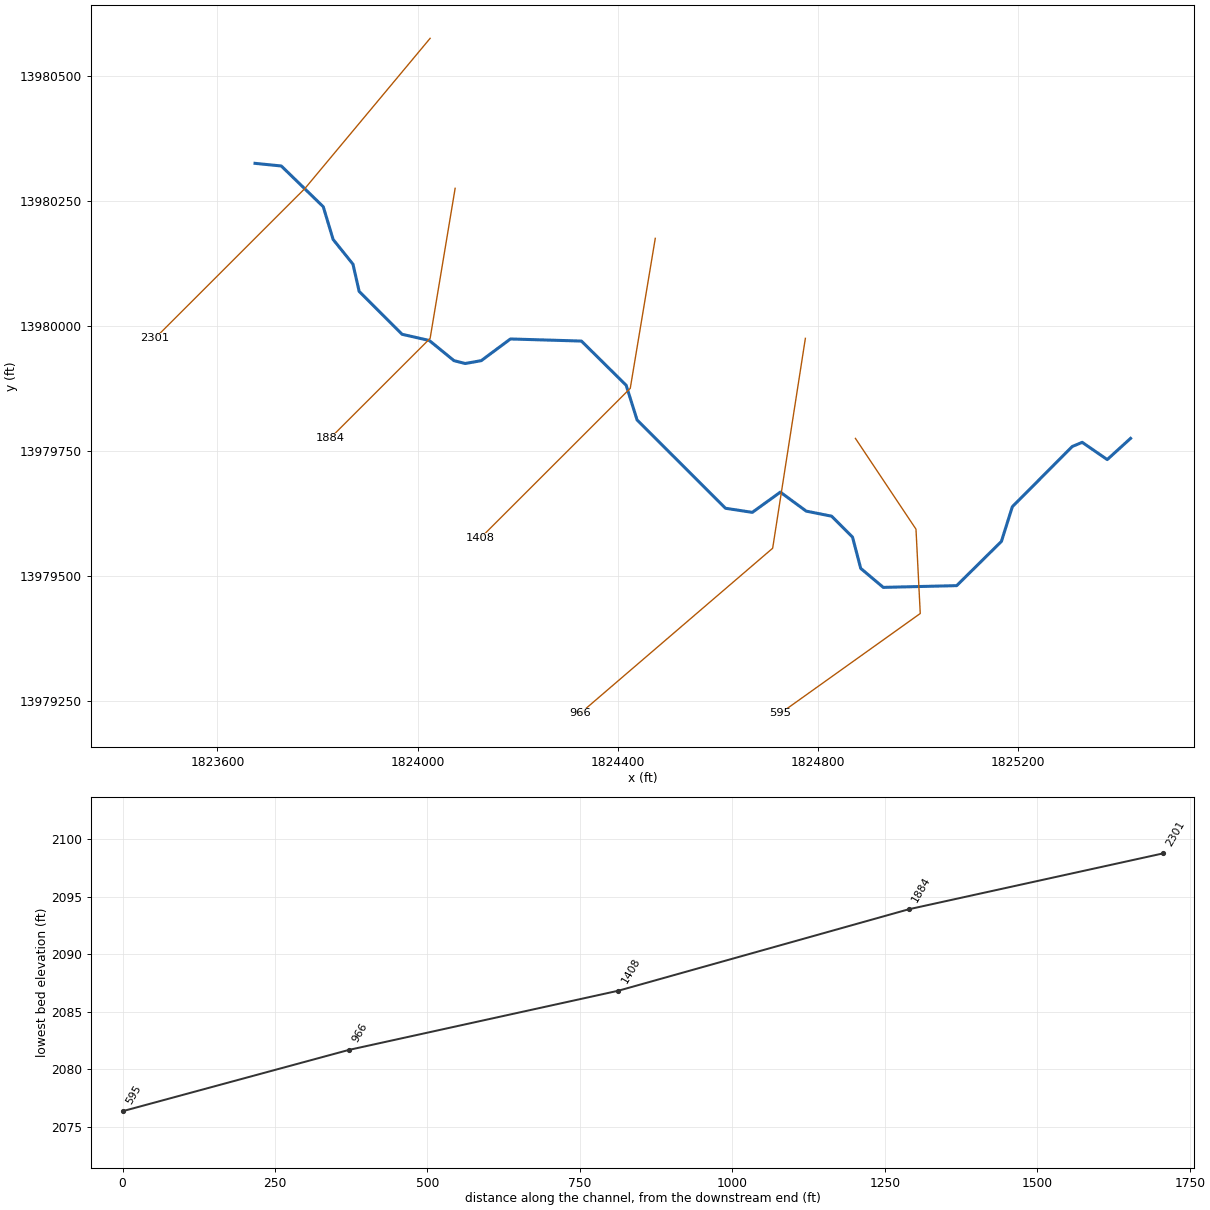
--- Stream0344.prj (project) ---

Proj Title=Stream0344 Base Level Engineering
Current Plan=p01
Default Exp/Contr=0.3,0.1
English Units
Geom File=g01
Flow File=f01
Plan File=p01
BEGIN DESCRIPTION:
Stream0344
END DESCRIPTION:

--- Stream0344.p01 (plan) ---

Plan Title=Multiple Run
Short Identifier=Multiple
Geom File=g01
Flow File=f01
Subcritical Flow
K Sum by GR= 0
Std Step Tol= 0.01
Critical Tol= 0.01
Num of Std Step Trials= 20
Max Error Tol= 0.3
Flow Tol Ratio= 0.001
Split Flow NTrial= 30
Split Flow Tol= 0.02
Split Flow Ratio= 0.02
Log Output Level= 0
Friction Slope Method= 1
Unsteady Friction Slope Method= 2
Unsteady Bridges Friction Slope Method= 1
Parabolic Critical Depth
Global Vel Dist=  1 , 1 , 1
Global Log Level= 0
CheckData=True
Encroach Param= -1, 0, 0, 0
BEGIN DESCRIPTION:
Multiple Run
END DESCRIPTION:

--- Stream0344.f01 (steady flow) ---

Flow Title=Multiple
Number of Profiles=7
Profile Names=10-year,25-year,50-year,1pct_min,100-year,1pct_plu,500-year
River Rch & RM= Stream0344,Reach-1,2301
     572     937    1270     834    1663    3319    2817
Boundary for River Rch & Prof#=Stream0344,Reach-1,1
Up Type=0
Dn Type=3
Dn Slope=0.005
Boundary for River Rch & Prof#=Stream0344,Reach-1,2
Up Type=0
Dn Type=3
Dn Slope=0.005
Boundary for River Rch & Prof#=Stream0344,Reach-1,3
Up Type=0
Dn Type=3
Dn Slope=0.005
Boundary for River Rch & Prof#=Stream0344,Reach-1,4
Up Type=0
Dn Type=3
Dn Slope=0.005
Boundary for River Rch & Prof#=Stream0344,Reach-1,5
Up Type=0
Dn Type=3
Dn Slope=0.005
Boundary for River Rch & Prof#=Stream0344,Reach-1,6
Up Type=0
Dn Type=3
Dn Slope=0.005
Boundary for River Rch & Prof#=Stream0344,Reach-1,7
Up Type=0
Dn Type=3
Dn Slope=0.005

--- Stream0344.g01 (geometry) ---

Geom Title=Existing Conditions

River Reach=Stream0344,Reach-1
Reach XY= 30
      1823675.00     13980325.00      1823727.54     13980319.70
      1823811.40     13980238.24      1823831.10     13980172.81
      1823870.81     13980123.26      1823883.13     13980068.93
      1823968.93     13979983.13      1824023.26     13979970.75
      1824072.80     13979930.34      1824095.17     13979924.70
      1824127.18     13979930.37      1824185.50     13979973.77
      1824327.46     13979969.55      1824416.85     13979881.07
      1824438.63     13979811.79      1824615.32     13979635.20
      1824668.95     13979626.98      1824725.00     13979667.44
      1824776.68     13979629.46      1824827.54     13979619.30
      1824869.24     13979577.51      1824885.63     13979514.96
      1824930.68     13979476.97      1825077.46     13979480.45
      1825166.85     13979568.93      1825188.63     13979638.21
      1825308.33     13979758.65      1825328.33     13979767.06
      1825378.33     13979732.52      1825425.00     13979775.00

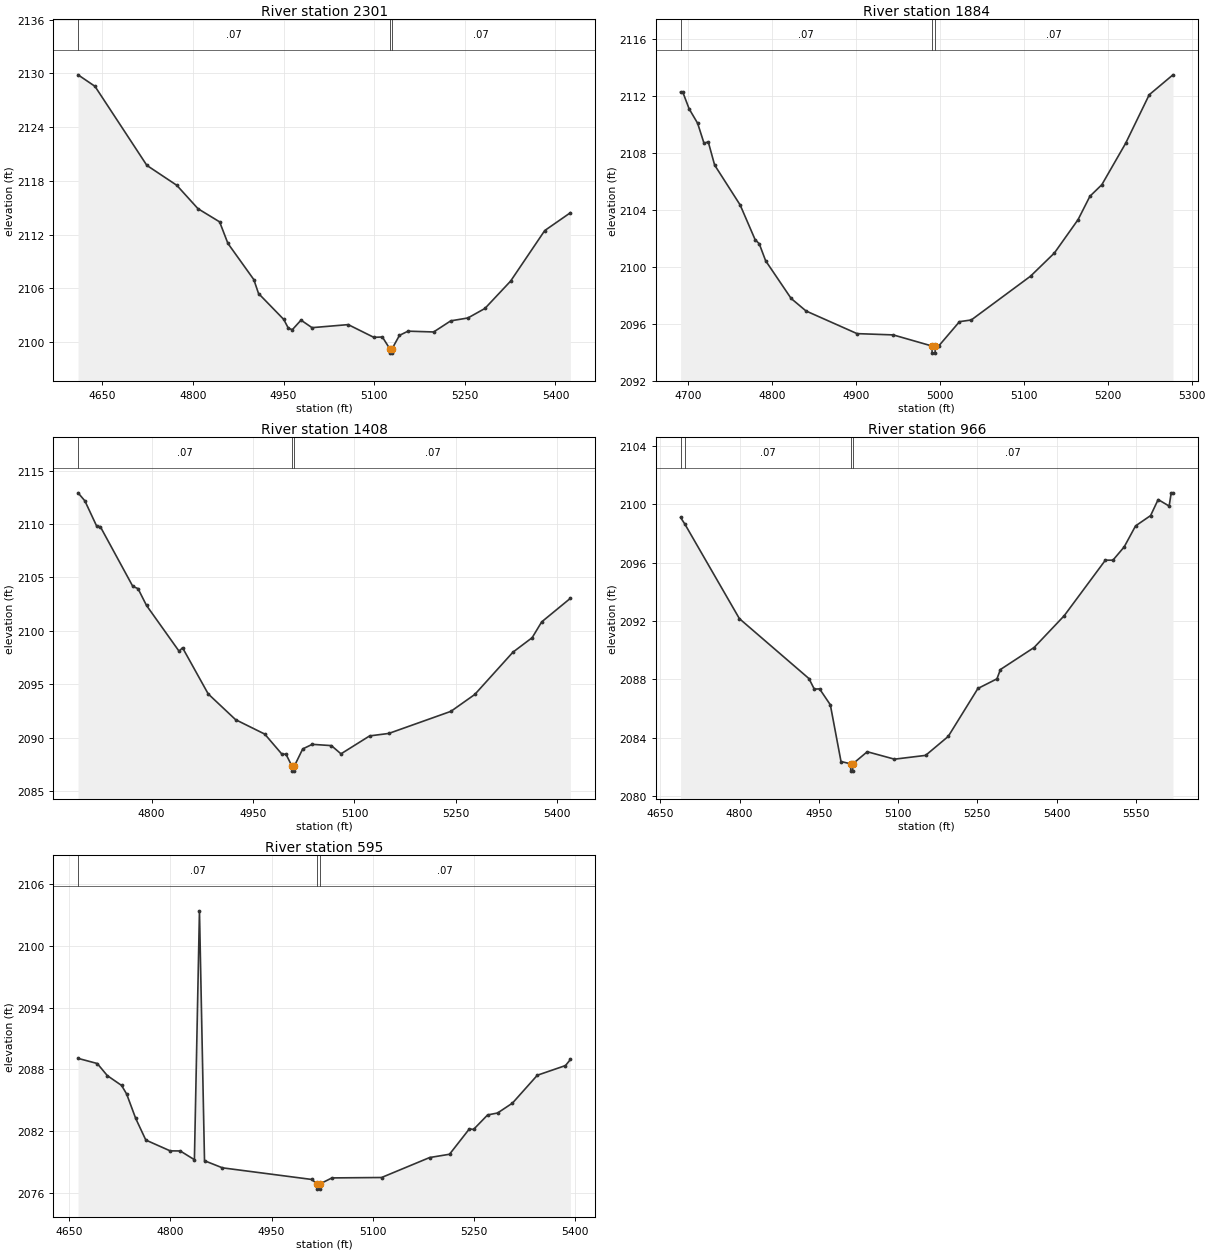
Type RM Length L Ch R = 1,2301,417,417,417
BEGIN DESCRIPTION:
Stream0344 5.0
END DESCRIPTION:
XS GIS Cut Line= 3
      1824024.99     13980574.99      1823775.00     13980275.00
      1823474.98     13979974.98
#Sta/Elev= 30
  4609.9 2129.83  4637.9 2128.55  4723.8 2119.73  4773.3 2117.51  4808.4 2114.90
  4844.2 2113.43  4857.9 2111.03  4900.8 2106.99  4908.6 2105.44  4950.3 2102.55
  4958.1 2101.55  4964.6 2101.41  4978.9 2102.47  4997.1 2101.63  5057.0 2101.97
  5099.4 2100.55  5113.5 2100.59  5125.7 2099.29  5125.9 2098.79  5129.4 2098.79
  5129.7 2099.29  5141.8 2100.77  5156.0 2101.24  5198.4 2101.15  5226.7 2102.39
  5255.0 2102.71  5283.2 2103.77  5325.7 2106.82  5382.2 2112.46  5424.7 2114.45
#Mann=3,-1,0
  4609.9    0.07       0  5125.7    0.05       0  5129.7    0.07       0
Bank Sta=5125.7,5129.7
Exp/Cntr=0.3,0.1

Type RM Length L Ch R = 1,1884,476,476,476
BEGIN DESCRIPTION:
Stream0344 4.0
END DESCRIPTION:
XS GIS Cut Line= 3
      1824075.01     13980275.05      1824025.00     13979975.00
      1823825.02     13979775.02
#Sta/Elev= 30
  4690.7 2112.27  4693.3 2112.27  4700.9 2111.09  4711.0 2110.08  4718.6 2108.68
  4723.7 2108.77  4731.3 2107.14  4761.7 2104.34  4779.5 2101.91  4784.5 2101.61
  4792.1 2100.42  4822.5 2097.77  4840.3 2096.89  4901.1 2095.30  4944.2 2095.21
  4990.4 2094.43  4990.6 2093.93  4994.1 2093.93  4994.4 2094.43  4998.4 2094.43
  5023.2 2096.14  5037.3 2096.26  5108.0 2099.34  5136.3 2100.96  5164.6 2103.31
  5178.7 2104.95  5192.9 2105.76  5221.2 2108.66  5249.4 2112.08  5277.7 2113.48
#Mann=3,-1,0
  4690.7    0.07       0  4990.4    0.05       0  4994.4    0.07       0
Bank Sta=4990.4,4994.4
Exp/Cntr=0.3,0.1

Type RM Length L Ch R = 1,1408,442,442,442
BEGIN DESCRIPTION:
Stream0344 3.0
END DESCRIPTION:
XS GIS Cut Line= 3
      1824474.99     13980174.96      1824425.00     13979875.00
      1824124.97     13979574.97
#Sta/Elev= 30
  4691.1 2112.92  4701.2 2112.17  4718.9 2109.77  4724.0 2109.76  4772.2 2104.15
  4779.8 2103.95  4792.4 2102.37  4840.6 2098.08  4845.7 2098.41  4883.7 2094.08
  4924.2 2091.67  4967.3 2090.32  4992.7 2088.44  4998.7 2088.44  5007.3 2087.35
  5007.6 2086.85  5011.1 2086.85  5011.3 2087.35  5023.5 2088.93  5037.6 2089.36
  5065.9 2089.24  5080.1 2088.47  5122.5 2090.15  5150.8 2090.38  5242.7 2092.45
  5278.0 2094.03  5334.6 2098.00  5362.9 2099.35  5377.0 2100.83  5419.5 2103.04
#Mann=3,-1,0
  4691.1    0.07       0  5007.3    0.05       0  5011.3    0.07       0
Bank Sta=5007.3,5011.3
Exp/Cntr=0.3,0.1

Type RM Length L Ch R = 1,966,371,371,371
BEGIN DESCRIPTION:
Stream0344 2.0
END DESCRIPTION:
XS GIS Cut Line= 3
      1824775.00     13979975.01      1824709.63     13979555.25
      1824324.99     13979224.99
#Sta/Elev= 30
  4688.4 2099.10  4696.6 2098.64  4799.7 2092.16  4931.3 2088.05  4941.4 2087.33
  4951.5 2087.34  4971.8 2086.25  4992.0 2082.36  5010.3 2082.20  5010.5 2081.70
  5014.0 2081.70  5014.3 2082.20  5041.7 2083.03  5093.2 2082.52  5152.1 2082.78
  5194.9 2084.08  5251.1 2087.37  5287.1 2088.03  5293.7 2088.67  5357.4 2090.18
  5414.4 2092.36  5492.3 2096.17  5506.6 2096.17  5527.9 2097.08  5549.4 2098.52
  5577.9 2099.23  5592.2 2100.33  5613.0 2099.88  5616.9 2100.79  5620.2 2100.79
#Mann=4,-1,0
  4688.4   0.035       0  4696.6    0.07       0  5010.3    0.05       0
  5014.3    0.07       0
Bank Sta=5010.3,5014.3
Exp/Cntr=0.3,0.1

Type RM Length L Ch R = 1,595,0,0,0
BEGIN DESCRIPTION:
Stream0344 1.0
END DESCRIPTION:
XS GIS Cut Line= 4
      1824875.03     13979774.96      1824996.08     13979593.38
      1825004.62     13979424.73      1824725.02     13979225.02
#Sta/Elev= 30
  4662.8 2089.08  4691.3 2088.58  4706.3 2087.40  4727.4 2086.45  4734.9 2085.62
  4748.4 2083.24  4763.4 2081.14  4799.5 2080.09  4814.5 2080.08  4835.5 2079.23
  4843.0 2103.42  4850.5 2079.13  4877.1 2078.44  5009.6 2077.31  5017.6 2076.87
  5017.8 2076.37  5021.3 2076.37  5021.6 2076.87  5039.6 2077.46  5113.3 2077.50
  5184.6 2079.44  5214.1 2079.76  5243.6 2082.23  5249.7 2082.17  5270.6 2083.58
  5285.4 2083.77  5307.5 2084.73  5344.4 2087.44  5386.2 2088.38  5393.5 2088.97
#Mann=3,-1,0
  4662.8    0.07       0  5017.6    0.05       0  5021.6    0.07       0
Bank Sta=5017.6,5021.6
Exp/Cntr=0.3,0.1

Chan Stop Cuts=-1