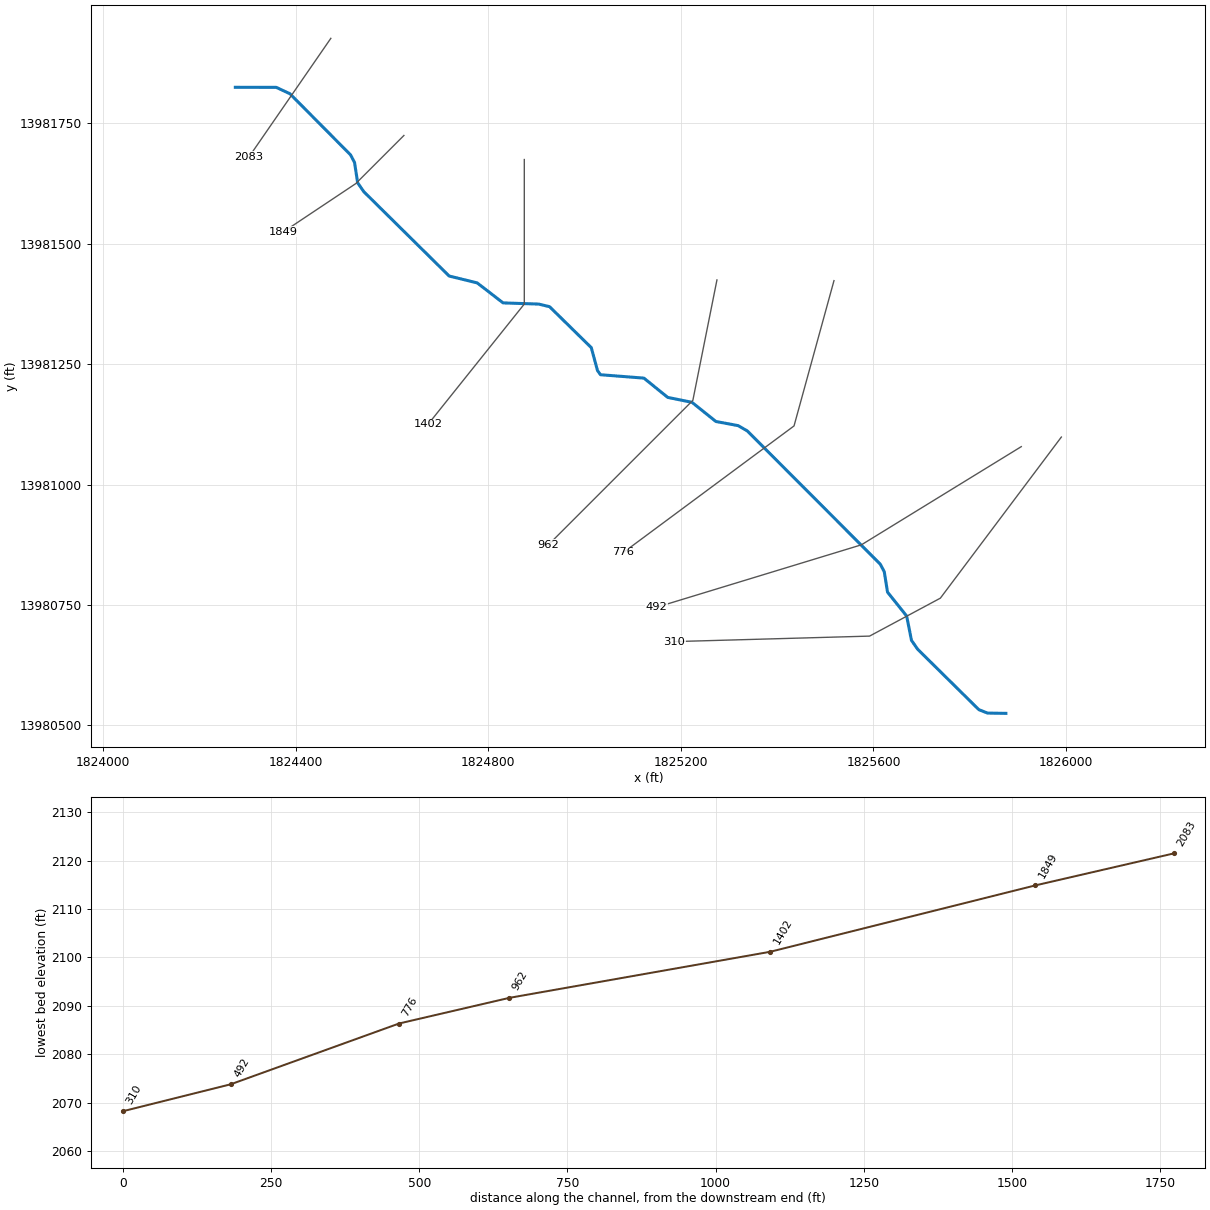
--- Stream0345.prj (project) ---

Proj Title=Stream0345 Base Level Engineering
Current Plan=p01
Default Exp/Contr=0.3,0.1
English Units
Geom File=g01
Flow File=f01
Plan File=p01
Y Axis Title=Elevation
X Axis Title(PF)=Main Channel Distance
X Axis Title(XS)=Station
BEGIN DESCRIPTION:
Stream0345
END DESCRIPTION:
DSS Export Rating Curves= 0
DSS Export Rating Curve Sorted= 0
DSS Export Volume Flow Curves= 0
DXF OffsetX= 0
DXF OffsetY= 0
DXF ScaleX= 1
DXF ScaleY= 10

--- Stream0345.p01 (plan) ---

Plan Title=Multiple Run
Short Identifier=Multiple
Geom File=g01
Flow File=f01
Subcritical Flow
K Sum by GR= 0
Std Step Tol= 0.01
Critical Tol= 0.01
Num of Std Step Trials= 20
Max Error Tol= 0.3
Flow Tol Ratio= 0.001
Split Flow NTrial= 30
Split Flow Tol= 0.02
Split Flow Ratio= 0.02
Log Output Level= 0
Friction Slope Method= 1
Unsteady Friction Slope Method= 2
Unsteady Bridges Friction Slope Method= 1
Parabolic Critical Depth
Global Vel Dist=  1 , 1 , 1
Global Log Level= 0
CheckData=True
Encroach Param= -1, 0, 0, 0
BEGIN DESCRIPTION:
Multiple Run
END DESCRIPTION:

--- Stream0345.f01 (steady flow) ---

Flow Title=Multiple
Program Version=4.10
Number of Profiles= 7
Profile Names=10-year,25-year,50-year,1pct_min,100-year,1pct_plu,500-year
River Rch & RM=Stream0345,Reach-1         ,2083
     288     450     593     379     756    1509    1212
Boundary for River Rch & Prof#=Stream0345,Reach-1         , 1
Up Type= 0
Dn Type= 3
Dn Slope=0.01
Boundary for River Rch & Prof#=Stream0345,Reach-1         , 2
Up Type= 0
Dn Type= 3
Dn Slope=0.01
Boundary for River Rch & Prof#=Stream0345,Reach-1         , 3
Up Type= 0
Dn Type= 3
Dn Slope=0.01
Boundary for River Rch & Prof#=Stream0345,Reach-1         , 4
Up Type= 0
Dn Type= 3
Dn Slope=0.01
Boundary for River Rch & Prof#=Stream0345,Reach-1         , 5
Up Type= 0
Dn Type= 3
Dn Slope=0.01
Boundary for River Rch & Prof#=Stream0345,Reach-1         , 6
Up Type= 0
Dn Type= 3
Dn Slope=0.01
Boundary for River Rch & Prof#=Stream0345,Reach-1         , 7
Up Type= 0
Dn Type= 3
Dn Slope=0.01
DSS Import GetInterval= 0
DSS Import GetPeak= 0
DSS Import FillOption= 0

--- Stream0345.g01 (geometry) ---

Geom Title=Existing Conditions

River Reach=Stream0345,Reach-1
Reach XY= 30
      1824275.00     13981825.00      1824359.95     13981824.88
      1824388.33     13981811.65      1824514.22     13981684.68
      1824522.47     13981668.95      1824528.98     13981626.65
      1824541.65     13981608.33      1824718.94     13981433.14
      1824777.17     13981418.86      1824830.97     13981377.33
      1824904.95     13981374.88      1824927.44     13981369.48
      1825014.11     13981284.40      1825027.00     13981236.74
      1825033.34     13981228.17      1825123.34     13981221.14
      1825172.82     13981181.11      1825223.28     13981170.84
      1825272.81     13981131.10      1825318.97     13981122.50
      1825338.21     13981111.38      1825614.24     13980834.68
      1825622.50     13980818.96      1825629.19     13980776.74
      1825668.90     13980727.19      1825678.95     13980676.63
      1825691.64     13980658.32      1825818.79     13980532.76
      1825836.84     13980525.59      1825875.00     13980525.00

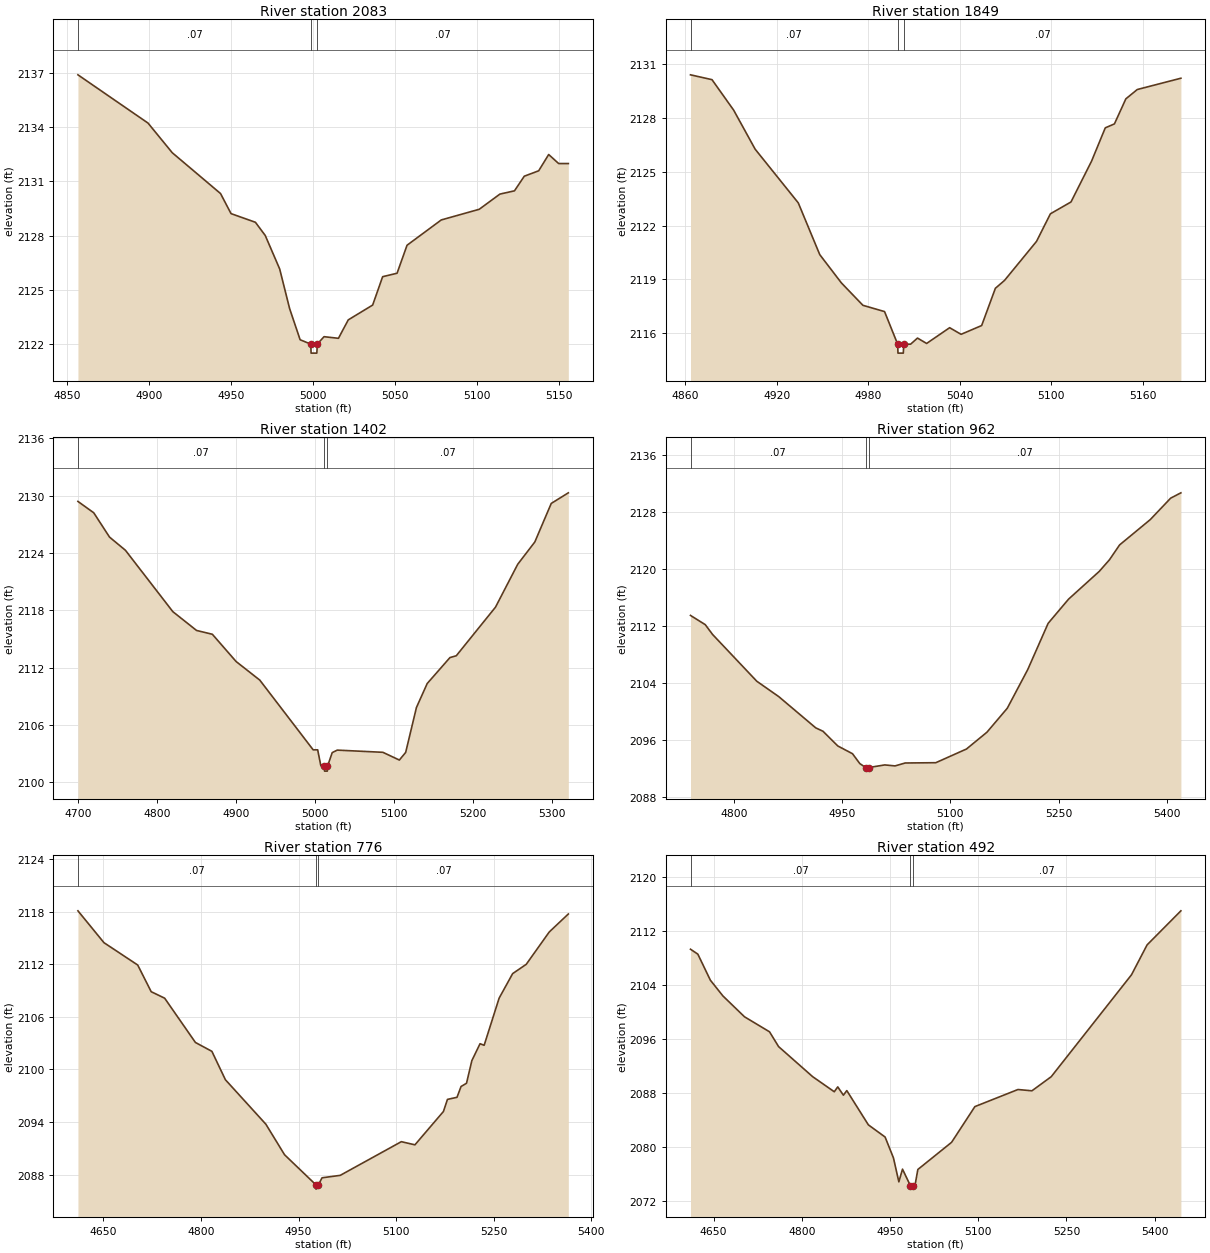
Type RM Length L Ch R = 1,2083,234,234,234
BEGIN DESCRIPTION:
Stream0345 5.0
END DESCRIPTION:
XS GIS Cut Line= 2
      1824473.26     13981926.69      1824303.14     13981680.19
#Sta/Elev= 30
  4856.5 2136.90  4899.3 2134.23  4914.1 2132.59  4943.6 2130.33  4950.0 2129.22
  4964.9 2128.74  4970.9 2128.01  4979.7 2126.16  4985.8 2123.96  4992.2 2122.24
  4998.7 2122.00  4998.9 2121.50  5002.4 2121.50  5002.7 2122.00  5006.8 2122.41
  5015.6 2122.32  5021.6 2123.34  5036.5 2124.16  5042.6 2125.73  5051.4 2125.92
  5057.5 2127.47  5078.4 2128.87  5101.6 2129.46  5114.2 2130.30  5123.1 2130.48
  5129.1 2131.29  5137.9 2131.59  5144.0 2132.49  5150.1 2131.99  5156.0 2131.99
#Mann=3,-1,0
  4856.5    0.07       0  4998.7    0.05       0  5002.7    0.07       0
Bank Sta=4998.7,5002.7
Exp/Cntr=0.3,0.1

Type RM Length L Ch R = 1,1849,447,447,447
BEGIN DESCRIPTION:
Stream0345 4.0
END DESCRIPTION:
XS GIS Cut Line= 3
      1824624.99     13981724.99      1824525.00     13981625.00
      1824374.99     13981524.99
#Sta/Elev= 30
  4863.4 2130.42  4877.5 2130.15  4891.7 2128.45  4905.8 2126.27  4934.1 2123.27
  4948.2 2120.38  4962.4 2118.80  4976.5 2117.55  4990.7 2117.20  4999.3 2115.38
  4999.5 2114.88  5003.0 2114.88  5003.3 2115.38  5007.8 2115.38  5012.3 2115.72
  5018.3 2115.42  5033.4 2116.30  5040.9 2115.93  5054.4 2116.42  5063.4 2118.50
  5069.4 2118.94  5090.4 2121.12  5099.5 2122.66  5113.0 2123.32  5126.5 2125.60
  5135.5 2127.46  5141.5 2127.68  5149.0 2129.08  5156.5 2129.60  5185.1 2130.23
#Mann=3,-1,0
  4863.4    0.07       0  4999.3    0.05       0  5003.3    0.07       0
Bank Sta=4999.3,5003.3
Exp/Cntr=0.3,0.1

Type RM Length L Ch R = 1,1402,440,440,440
BEGIN DESCRIPTION:
Stream0345 3.0
END DESCRIPTION:
XS GIS Cut Line= 3
      1824875.00     13981675.04      1824875.00     13981375.00
      1824674.99     13981124.99
#Sta/Elev= 30
  4700.0 2129.41  4720.0 2128.22  4740.0 2125.67  4760.0 2124.30  4820.0 2117.87
  4850.0 2115.90  4870.0 2115.50  4900.0 2112.65  4930.0 2110.70  4997.5 2103.40
  5003.2 2103.40  5007.2 2101.74  5011.6 2101.67  5011.9 2101.17  5015.4 2101.17
  5015.6 2101.67  5021.6 2103.11  5028.0 2103.37  5085.7 2103.14  5106.5 2102.33
  5114.5 2103.13  5128.1 2107.83  5141.7 2110.34  5170.5 2113.06  5178.5 2113.25
  5228.1 2118.34  5256.2 2122.83  5277.8 2125.16  5298.6 2129.20  5320.2 2130.31
#Mann=3,-1,0
  4700.0    0.07       0  5011.6    0.05       0  5015.6    0.07       0
Bank Sta=5011.6,5015.6
Exp/Cntr=0.3,0.1

Type RM Length L Ch R = 1,962,186,186,186
BEGIN DESCRIPTION:
Stream0345 2.0
END DESCRIPTION:
XS GIS Cut Line= 3
      1825275.01     13981425.04      1825225.00     13981175.00
      1824924.97     13980874.97
#Sta/Elev= 30
  4740.0 2113.47  4760.4 2112.18  4770.6 2110.80  4831.8 2104.25  4862.4 2102.08
  4913.4 2097.72  4923.6 2097.23  4944.0 2095.18  4964.4 2094.09  4974.6 2092.70
  4982.8 2092.15  4983.0 2091.65  4986.5 2091.65  4986.8 2092.15  5009.1 2092.52
  5023.3 2092.38  5037.4 2092.79  5079.8 2092.83  5122.3 2094.75  5150.6 2097.10
  5178.8 2100.46  5207.1 2105.87  5235.4 2112.36  5263.7 2115.75  5306.1 2119.63
  5320.3 2121.26  5334.4 2123.35  5376.8 2126.89  5405.1 2129.90  5419.3 2130.65
#Mann=3,-1,0
  4740.0    0.07       0  4982.8    0.05       0  4986.8    0.07       0
Bank Sta=4982.8,4986.8
Exp/Cntr=0.3,0.1

Type RM Length L Ch R = 1,776,284,284,284
BEGIN DESCRIPTION:
Mapping XS acf21f71
END DESCRIPTION:
XS GIS Cut Line= 3
      1825518.04     13981423.57      1825435.07     13981121.86
      1825080.90     13980859.29
#Sta/Elev= 30
  4610.9 2118.08  4650.9 2114.45  4702.8 2111.90  4723.5 2108.86  4744.2 2108.12
  4791.5 2103.07  4816.8 2102.06  4837.6 2098.82  4899.8 2093.75  4928.5 2090.27
  4976.6 2086.85  4976.9 2086.35  4980.6 2086.85  4986.1 2087.64  5014.1 2087.92
  5108.0 2091.76  5128.9 2091.40  5172.7 2095.20  5178.9 2096.58  5193.6 2096.82
  5199.8 2098.05  5208.2 2098.42  5216.4 2101.00  5229.0 2102.93  5235.3 2102.75
  5258.3 2108.12  5279.1 2110.92  5300.0 2111.98  5335.4 2115.67  5364.7 2117.72
#Mann=3,-1,0
  4610.9    0.07       0  4976.6    0.05       0  4980.6    0.07       0
Bank Sta=4976.6,4980.6
Exp/Cntr=0.3,0.1

Type RM Length L Ch R = 1,492,182,182,182
BEGIN DESCRIPTION:
Stream0345 1.0
END DESCRIPTION:
XS GIS Cut Line= 3
      1825906.94     13981078.87      1825575.00     13980875.00
      1825149.96     13980745.44
#Sta/Elev= 30
  4610.7 2109.34  4623.2 2108.61  4644.5 2104.75  4665.8 2102.42  4702.5 2099.33
  4745.1 2097.10  4760.5 2094.91  4818.5 2090.45  4855.2 2088.22  4861.1 2088.94
  4870.7 2087.71  4876.5 2088.39  4913.2 2083.31  4941.6 2081.51  4955.8 2078.42
  4965.0 2074.87  4971.2 2076.75  4984.7 2074.29  4984.9 2073.79  4988.7 2074.29
  4992.5 2074.37  4997.3 2076.70  5054.7 2080.73  5094.3 2086.02  5167.5 2088.55
  5191.3 2088.36  5224.1 2090.45  5360.6 2105.55  5387.1 2109.98  5444.6 2115.03
#Mann=3,-1,0
  4610.7    0.07       0  4984.7    0.05       0  4988.7    0.07       0
Bank Sta=4984.7,4988.7
Exp/Cntr=0.3,0.1

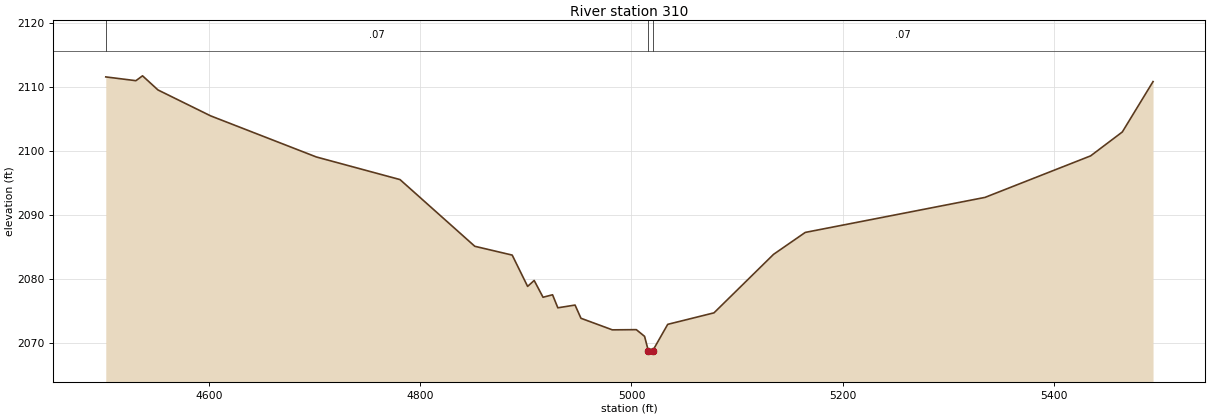
Type RM Length L Ch R = 1,310,0,0,0
BEGIN DESCRIPTION:
Stream0345 0.0
END DESCRIPTION:
XS GIS Cut Line= 4
      1825990.16     13981098.77      1825738.93     13980764.26
      1825591.93     13980685.45      1825185.93     13980674.01
#Sta/Elev= 30
  4502.4 2111.61  4530.9 2111.02  4537.2 2111.78  4551.8 2109.57  4601.7 2105.51
  4701.7 2099.08  4780.9 2095.54  4851.7 2085.10  4887.1 2083.72  4901.7 2078.82
  4907.9 2079.75  4916.3 2077.12  4925.3 2077.51  4930.3 2075.47  4946.6 2075.90
  4952.2 2073.83  4981.9 2072.02  5004.6 2072.05  5012.4 2071.00  5016.0 2068.72
  5016.3 2068.22  5020.0 2068.72  5034.3 2072.88  5078.1 2074.68  5134.5 2083.84
  5164.5 2087.27  5334.6 2092.75  5434.6 2099.25  5464.6 2102.99  5493.7 2110.88
#Mann=3,-1,0
  4502.4    0.07       0  5016.0    0.05       0  5020.0    0.07       0
Bank Sta=5016,5020
Exp/Cntr=0.3,0.1

Chan Stop Cuts=-1