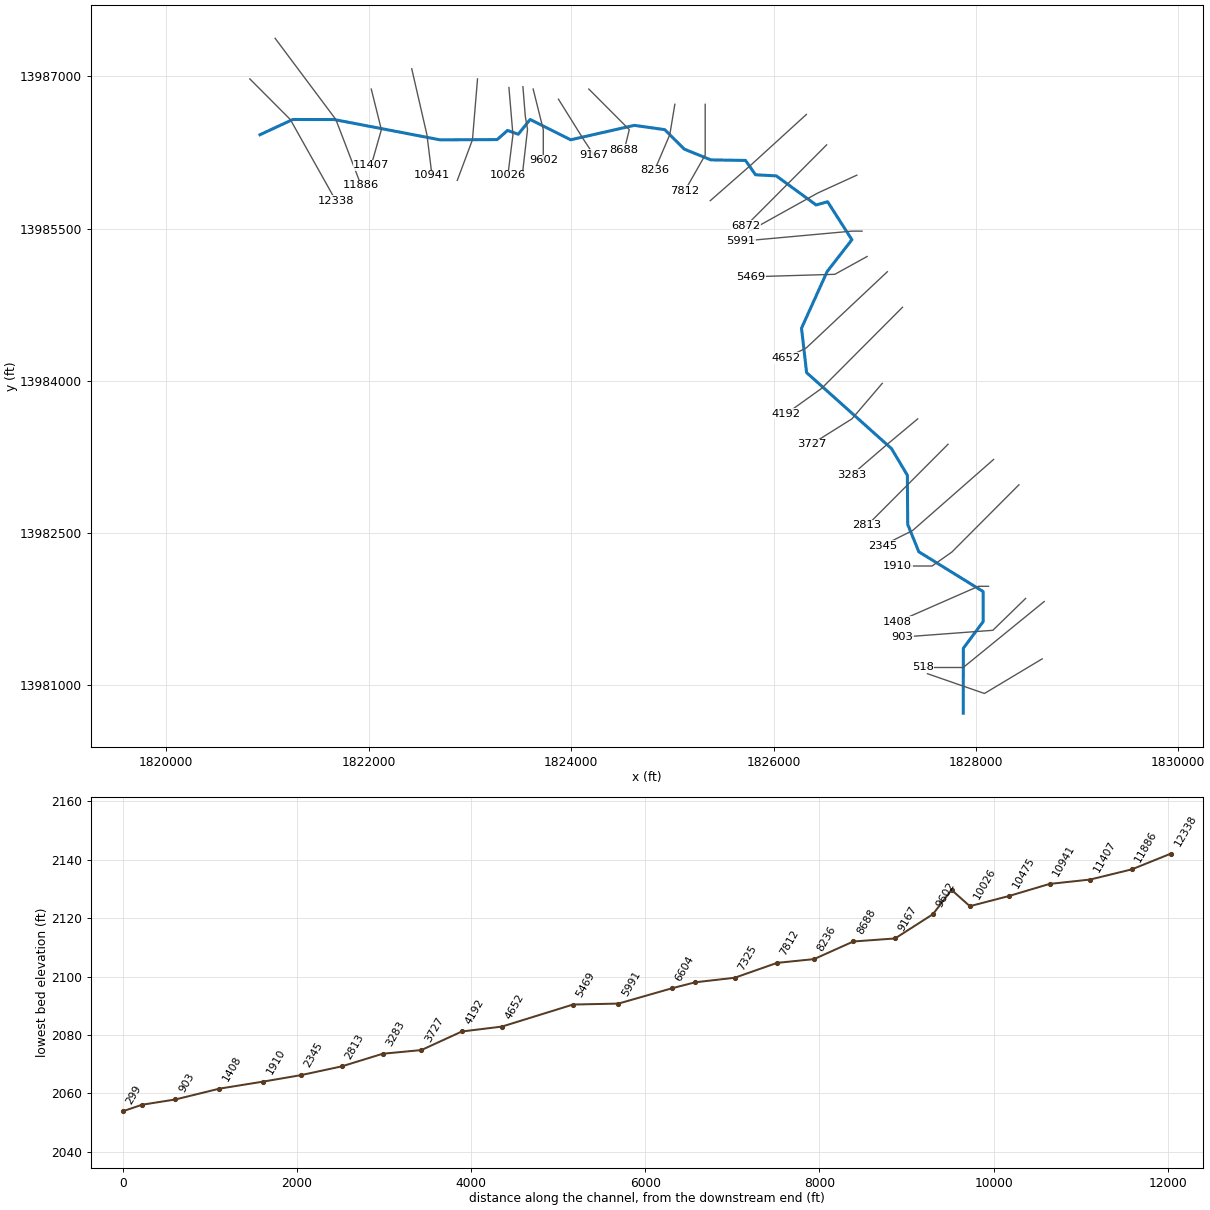
--- Stream0346.prj (project) ---

Proj Title=Stream0346 Base Level Engineering
Current Plan=p01
Default Exp/Contr=0.3,0.1
English Units
Geom File=g01
Flow File=f01
Plan File=p01
BEGIN DESCRIPTION:
Stream0346
END DESCRIPTION:

--- Stream0346.p01 (plan) ---

Plan Title=Multiple Run
Short Identifier=Multiple
Geom File=g01
Flow File=f01
Subcritical Flow
K Sum by GR= 0
Std Step Tol= 0.01
Critical Tol= 0.01
Num of Std Step Trials= 20
Max Error Tol= 0.3
Flow Tol Ratio= 0.001
Split Flow NTrial= 30
Split Flow Tol= 0.02
Split Flow Ratio= 0.02
Log Output Level= 0
Friction Slope Method= 1
Unsteady Friction Slope Method= 2
Unsteady Bridges Friction Slope Method= 1
Parabolic Critical Depth
Global Vel Dist=  1 , 1 , 1
Global Log Level= 0
CheckData=True
Encroach Param= -1, 0, 0, 0
BEGIN DESCRIPTION:
Multiple Run
END DESCRIPTION:

--- Stream0346.f01 (steady flow) ---

Flow Title=Multiple
Number of Profiles=7
Profile Names=10-year,25-year,50-year,1pct_min,100-year,1pct_plu,500-year
River Rch & RM= Stream0346,Reach-1,12338
    1352    2317    3236    2180    4350    8679    7772
River Rch & RM= Stream0346,Reach-1,8236
    1940    3388    4793    3265    6516   13000   11915
River Rch & RM= Stream0346,Reach-1,6604
    2417    4264    6072    4161    8302   16566   15365
River Rch & RM= Stream0346,Reach-1,2345
    2468    4352    6194    4243    8465   16890   15648
Boundary for River Rch & Prof#=Stream0346,Reach-1,1
Up Type=0
Dn Type=3
Dn Slope=0.005
Boundary for River Rch & Prof#=Stream0346,Reach-1,2
Up Type=0
Dn Type=3
Dn Slope=0.005
Boundary for River Rch & Prof#=Stream0346,Reach-1,3
Up Type=0
Dn Type=3
Dn Slope=0.005
Boundary for River Rch & Prof#=Stream0346,Reach-1,4
Up Type=0
Dn Type=3
Dn Slope=0.005
Boundary for River Rch & Prof#=Stream0346,Reach-1,5
Up Type=0
Dn Type=3
Dn Slope=0.005
Boundary for River Rch & Prof#=Stream0346,Reach-1,6
Up Type=0
Dn Type=3
Dn Slope=0.005
Boundary for River Rch & Prof#=Stream0346,Reach-1,7
Up Type=0
Dn Type=3
Dn Slope=0.005

--- Stream0346.g01 (geometry) ---

Geom Title=Existing Conditions

River Reach=Stream0346,Reach-1
Reach XY= 30
      1820925.00     13986425.00      1821249.92     13986575.20
      1821659.78     13986574.48      1822704.85     13986374.64
      1823269.15     13986377.07      1823371.60     13986467.16
      1823477.54     13986430.01      1823595.06     13986575.52
      1823995.03     13986375.07      1824625.00     13986517.44
      1824925.00     13986475.00      1825118.83     13986282.86
      1825380.93     13986177.24      1825723.75     13986171.55
      1825822.30     13986030.36      1826027.45     13986019.54
      1826421.60     13985732.83      1826534.68     13985764.80
      1826774.63     13985390.27      1826530.52     13985077.43
      1826276.80     13984518.89      1826327.06     13984080.85
      1827166.86     13983331.06      1827322.94     13983069.14
      1827326.22     13982585.50      1827435.75     13982315.29
      1828071.46     13981923.54      1828071.46     13981626.46
      1827876.20     13981364.50      1827875.00     13980725.00

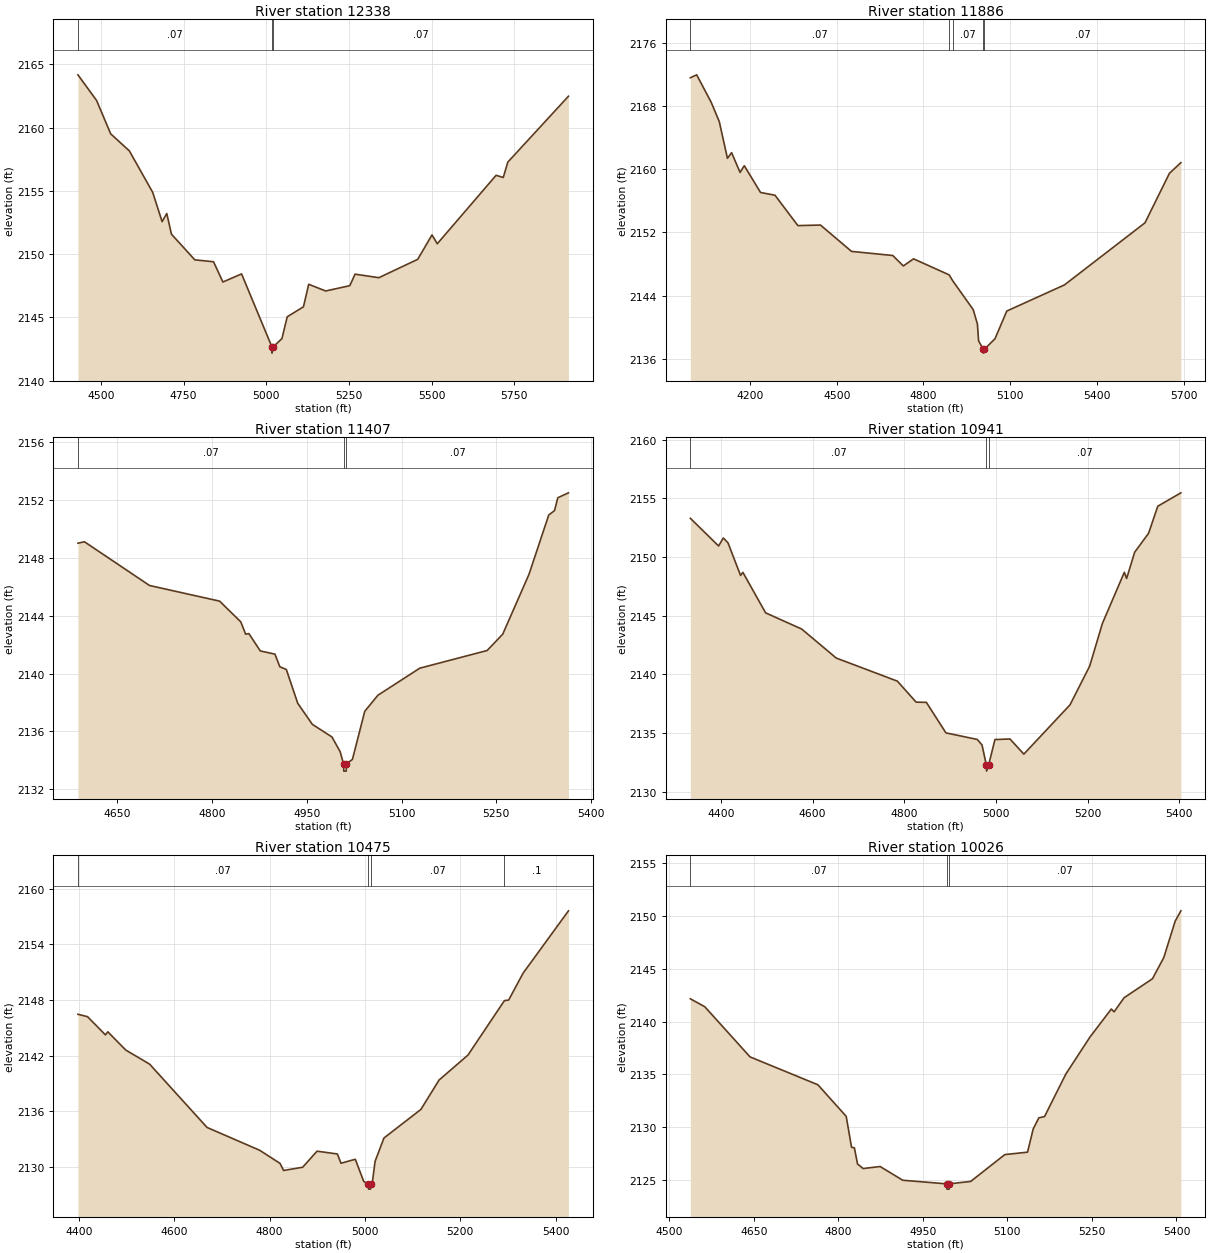
Type RM Length L Ch R = 1,12338,452,452,452
BEGIN DESCRIPTION:
Stream0346 25.0
END DESCRIPTION:
XS GIS Cut Line= 3
      1820825.02     13986974.98      1821225.00     13986575.00
      1821674.99     13985775.03
#Sta/Elev= 30
  4430.2 2164.17  4486.7 2162.14  4529.2 2159.51  4585.7 2158.16  4656.4 2154.88
  4684.7 2152.57  4698.9 2153.21  4713.0 2151.58  4783.7 2149.55  4840.3 2149.40
  4868.6 2147.80  4925.1 2148.44  5016.7 2142.68  5017.0 2142.18  5020.9 2142.68
  5047.2 2143.33  5063.1 2145.05  5112.2 2145.84  5128.1 2147.62  5179.4 2147.09
  5252.4 2147.51  5268.3 2148.42  5340.1 2148.14  5457.7 2149.59  5501.0 2151.52
  5516.9 2150.82  5694.8 2156.23  5716.5 2156.06  5730.2 2157.27  5913.7 2162.48
#Mann=3,-1,0
  4430.2    0.07       0  5016.7    0.05       0  5020.9    0.07       0
Bank Sta=5016.7,5020.9
Exp/Cntr=0.3,0.1

Type RM Length L Ch R = 1,11886,479,479,479
BEGIN DESCRIPTION:
Stream0346 24.0
END DESCRIPTION:
XS GIS Cut Line= 3
      1821074.98     13987375.02      1821675.00     13986575.00
      1821924.98     13985925.04
#Sta/Elev= 30
  3993.9 2171.56  4015.8 2171.93  4065.8 2168.47  4093.9 2166.02  4122.1 2161.38
  4136.6 2162.09  4165.8 2159.59  4180.4 2160.44  4236.6 2157.06  4286.6 2156.71
  4365.8 2152.87  4443.9 2152.94  4551.2 2149.61  4693.9 2149.09  4730.4 2147.77
  4765.8 2148.67  4889.0 2146.64  4901.5 2145.88  4972.1 2142.25  4986.6 2140.43
  4990.8 2138.29  5006.7 2137.25  5007.0 2136.75  5011.1 2137.25  5047.5 2138.57
  5088.2 2142.07  5287.5 2145.37  5566.1 2153.22  5650.7 2159.48  5690.3 2160.83
#Mann=5,-1,0
  3993.9    0.07       0  4889.0     0.1       0  4901.5    0.07       0
  5006.7    0.05       0  5011.1    0.07       0
Bank Sta=5006.7,5011.1
Exp/Cntr=0.3,0.1

Type RM Length L Ch R = 1,11407,466,466,466
BEGIN DESCRIPTION:
Stream0346 23.0
END DESCRIPTION:
XS GIS Cut Line= 3
      1822025.01     13986874.96      1822125.00     13986475.00
      1822024.99     13986124.98
#Sta/Elev= 30
  4587.8 2149.00  4598.1 2149.10  4701.1 2146.08  4812.0 2145.00  4845.5 2143.57
  4853.2 2142.72  4858.3 2142.76  4876.4 2141.56  4899.6 2141.34  4907.3 2140.47
  4917.6 2140.28  4935.7 2137.94  4958.8 2136.49  4989.8 2135.62  5002.7 2134.61
  5008.2 2133.76  5008.5 2133.26  5012.4 2133.26  5012.7 2133.76  5022.2 2134.07
  5041.7 2137.39  5062.5 2138.50  5128.8 2140.37  5235.4 2141.59  5260.1 2142.72
  5301.7 2146.86  5332.9 2150.95  5342.0 2151.25  5347.2 2152.14  5364.1 2152.48
#Mann=3,-1,0
  4587.8    0.07       0  5008.2    0.05       0  5012.7    0.07       0
Bank Sta=5008.2,5012.7
Exp/Cntr=0.3,0.1

Type RM Length L Ch R = 1,10941,466,466,466
BEGIN DESCRIPTION:
Stream0346 22.0
END DESCRIPTION:
XS GIS Cut Line= 3
      1822425.00     13987075.02      1822575.00     13986425.00
      1822625.00     13986025.01
#Sta/Elev= 30
  4333.3 2153.31  4394.9 2150.95  4405.2 2151.63  4415.4 2151.22  4442.8 2148.44
  4447.9 2148.70  4497.5 2145.25  4576.2 2143.87  4651.5 2141.40  4784.9 2139.43
  4825.9 2137.64  4848.2 2137.62  4890.9 2135.02  4959.3 2134.46  4969.6 2133.99
  4979.2 2132.26  4979.6 2131.76  4983.9 2132.26  4997.8 2134.45  5030.6 2134.50
  5060.9 2133.21  5161.6 2137.41  5204.5 2140.71  5232.2 2144.34  5280.1 2148.71
  5285.1 2148.18  5302.7 2150.42  5333.0 2152.03  5353.1 2154.34  5403.5 2155.48
#Mann=3,-1,0
  4333.3    0.07       0  4979.2    0.05       0  4983.9    0.07       0
Bank Sta=4979.2,4983.9
Exp/Cntr=0.3,0.1

Type RM Length L Ch R = 1,10475,449,449,449
BEGIN DESCRIPTION:
Stream0346 21.0
END DESCRIPTION:
XS GIS Cut Line= 3
      1823075.00     13986975.01      1823025.00     13986375.00
      1822875.00     13985974.99
#Sta/Elev= 30
  4397.9 2146.47  4418.0 2146.21  4455.6 2144.25  4460.6 2144.58  4498.3 2142.61
  4548.4 2141.09  4668.8 2134.27  4779.2 2131.81  4821.9 2130.40  4829.4 2129.63
  4869.5 2129.98  4899.6 2131.71  4942.3 2131.41  4949.8 2130.41  4979.9 2130.84
  4997.5 2128.46  5007.4 2128.12  5007.8 2127.62  5011.8 2127.62  5012.1 2128.12
  5015.1 2128.12  5021.4 2130.61  5040.0 2133.13  5117.5 2136.21  5155.7 2139.38
  5216.3 2142.07  5292.8 2147.94  5301.7 2148.00  5332.0 2150.90  5427.2 2157.62
#Mann=4,-1,0
  4397.9    0.07       0  5007.4    0.05       0  5012.1    0.07       0
  5292.8     0.1       0
Bank Sta=5007.4,5012.1
Exp/Cntr=0.3,0.1

Type RM Length L Ch R = 1,10026,210,210,210
BEGIN DESCRIPTION:
Stream0346 20.0
END DESCRIPTION:
XS GIS Cut Line= 3
      1823385.36     13986890.49      1823425.00     13986425.00
      1823375.00     13986024.98
#Sta/Elev= 30
  4537.5 2142.16  4563.1 2141.41  4643.4 2136.66  4763.8 2134.02  4814.0 2131.03
  4823.5 2128.10  4828.5 2128.05  4834.1 2126.52  4844.1 2126.09  4874.2 2126.28
  4914.3 2124.98  4992.2 2124.64  4992.6 2124.14  4996.7 2124.14  4997.0 2124.64
  5034.9 2124.87  5095.4 2127.41  5135.7 2127.64  5145.8 2129.84  5155.8 2130.89
  5165.9 2131.01  5203.7 2135.04  5246.5 2138.54  5284.3 2141.19  5289.4 2140.93
  5307.0 2142.26  5357.4 2144.06  5377.5 2146.07  5397.7 2149.52  5407.8 2150.49
#Mann=3,-1,0
  4537.5    0.07       0  4992.2    0.05       0  4997.0    0.07       0
Bank Sta=4992.2,4997
Exp/Cntr=0.3,0.1

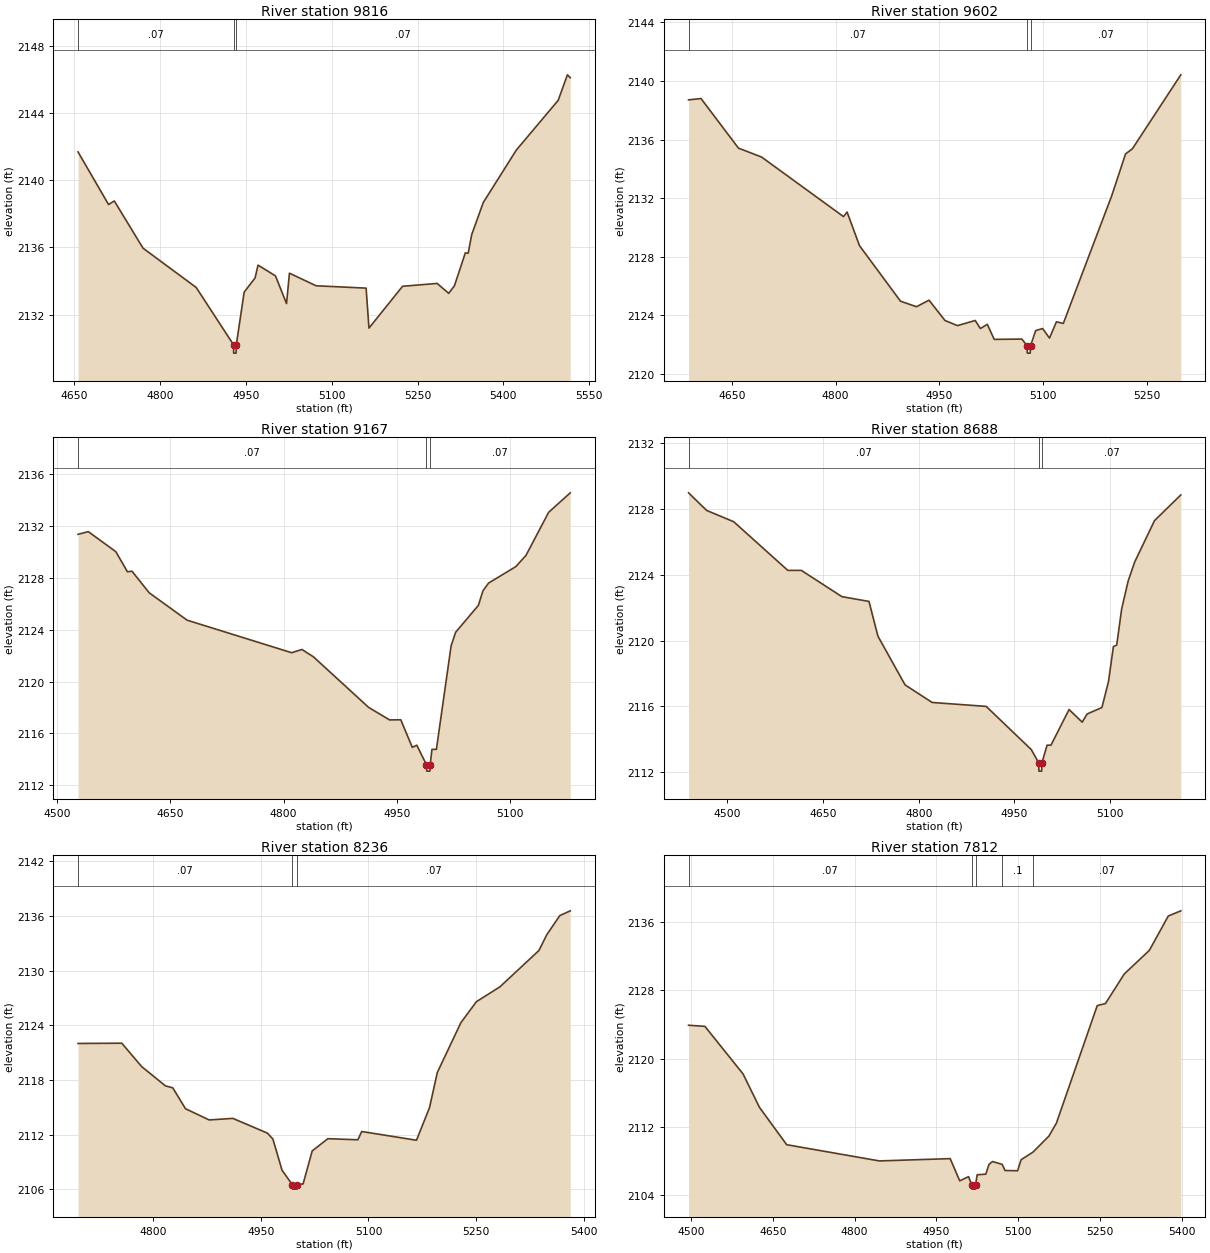
Type RM Length L Ch R = 1,9816,214,214,214
BEGIN DESCRIPTION:
Mapping XS 35676e3b
END DESCRIPTION:
XS GIS Cut Line= 4
      1823523.76     13986898.18      1823546.95     13986607.79
      1823569.31     13986477.84      1823519.54     13986044.05
#Sta/Elev= 30
  4657.0 2141.69  4710.3 2138.56  4720.4 2138.77  4770.5 2135.96  4863.4 2133.62
  4928.6 2130.21  4928.9 2129.71  4933.1 2129.71  4933.5 2130.21  4947.2 2133.34
  4966.3 2134.19  4971.4 2134.95  5001.9 2134.31  5021.2 2132.66  5026.3 2134.47
  5072.9 2133.72  5160.2 2133.58  5165.2 2131.20  5223.9 2133.69  5284.3 2133.86
  5304.5 2133.27  5314.5 2133.72  5333.5 2135.68  5338.5 2135.66  5344.7 2136.77
  5364.9 2138.68  5422.6 2141.80  5495.7 2144.76  5511.8 2146.28  5516.8 2146.11
#Mann=3,-1,0
  4657.0    0.07       0  4928.6    0.05       0  4933.5    0.07       0
Bank Sta=4928.6,4933.5
Exp/Cntr=0.3,0.1

Type RM Length L Ch R = 1,9602,435,435,435
BEGIN DESCRIPTION:
Stream0346 19.0
END DESCRIPTION:
XS GIS Cut Line= 3
      1823625.00     13986875.00      1823725.00     13986475.00
      1823725.00     13986175.01
#Sta/Elev= 30
  4587.3 2138.71  4605.3 2138.80  4659.5 2135.41  4693.0 2134.80  4811.5 2130.73
  4816.7 2131.04  4834.7 2128.74  4894.0 2124.95  4917.2 2124.57  4935.2 2125.02
  4958.4 2123.63  4976.4 2123.28  5002.1 2123.63  5009.6 2123.08  5019.6 2123.37
  5029.6 2122.34  5069.6 2122.36  5077.2 2121.90  5077.5 2121.40  5081.7 2121.40
  5082.1 2121.90  5089.6 2122.94  5099.6 2123.08  5109.6 2122.43  5119.6 2123.54
  5129.6 2123.43  5199.6 2132.15  5219.6 2135.01  5229.6 2135.37  5299.6 2140.42
#Mann=3,-1,0
  4587.3    0.07       0  5077.2    0.05       0  5082.1    0.07       0
Bank Sta=5077.2,5082.1
Exp/Cntr=0.3,0.1

Type RM Length L Ch R = 1,9167,479,479,479
BEGIN DESCRIPTION:
Stream0346 18.0
END DESCRIPTION:
XS GIS Cut Line= 3
      1823875.00     13986775.01      1824125.00     13986375.00
      1824225.01     13986224.99
#Sta/Elev= 30
  4527.8 2131.35  4541.4 2131.56  4577.9 2130.01  4593.3 2128.46  4599.2 2128.51
  4622.1 2126.84  4672.3 2124.73  4810.8 2122.22  4824.4 2122.47  4839.7 2121.90
  4912.8 2118.00  4940.5 2117.04  4955.3 2117.05  4970.6 2114.92  4976.5 2115.09
  4989.3 2113.59  4989.7 2113.09  4993.9 2113.09  4994.3 2113.59  4996.6 2114.77
  5002.5 2114.77  5022.0 2122.76  5028.0 2123.80  5058.1 2125.87  5064.1 2126.99
  5071.6 2127.59  5107.7 2128.86  5121.2 2129.73  5151.2 2133.05  5179.8 2134.55
#Mann=3,-1,0
  4527.8    0.07       0  4989.3    0.05       0  4994.3    0.07       0
Bank Sta=4989.3,4994.3
Exp/Cntr=0.3,0.1

Type RM Length L Ch R = 1,8688,452,452,452
BEGIN DESCRIPTION:
Stream0346 17.0
END DESCRIPTION:
XS GIS Cut Line= 3
      1824174.96     13986875.04      1824575.00     13986475.00
      1824525.00     13986274.99
#Sta/Elev= 30
  4439.0 2128.99  4467.3 2127.92  4509.8 2127.23  4594.6 2124.27  4615.8 2124.27
  4679.5 2122.67  4721.9 2122.38  4736.0 2120.26  4778.5 2117.30  4820.9 2116.23
  4905.7 2115.99  4976.5 2113.36  4988.1 2112.55  4988.4 2112.05  4992.7 2112.05
  4993.1 2112.55  5001.2 2113.63  5007.3 2113.63  5035.7 2115.80  5056.3 2115.03
  5064.0 2115.53  5087.2 2115.92  5097.5 2117.50  5105.2 2119.63  5110.4 2119.72
  5118.1 2121.91  5128.4 2123.63  5138.7 2124.79  5169.7 2127.30  5210.9 2128.86
#Mann=3,-1,0
  4439.0    0.07       0  4988.1    0.05       0  4993.1    0.07       0
Bank Sta=4988.1,4993.1
Exp/Cntr=0.3,0.1

Type RM Length L Ch R = 1,8236,424,424,424
BEGIN DESCRIPTION:
Stream0346 16.0
END DESCRIPTION:
XS GIS Cut Line= 3
      1825025.01     13986725.04      1824975.00     13986425.00
      1824824.99     13986074.97
#Sta/Elev= 30
  4695.8 2122.01  4756.7 2122.04  4784.5 2119.46  4817.5 2117.35  4827.6 2117.14
  4845.4 2114.84  4878.3 2113.61  4911.3 2113.78  4959.4 2112.16  4967.0 2111.51
  4979.7 2108.09  4993.9 2106.51  4994.4 2106.01  5000.5 2106.01  5001.0 2106.51
  5009.0 2106.58  5021.7 2110.21  5043.5 2111.55  5085.2 2111.43  5090.6 2112.34
  5166.8 2111.38  5184.9 2114.95  5195.8 2118.82  5228.5 2124.28  5250.2 2126.60
  5282.9 2128.23  5337.2 2132.22  5348.1 2133.95  5366.3 2136.06  5380.8 2136.58
#Mann=3,-1,0
  4695.8    0.07       0  4993.9    0.05       0  5001.0    0.07       0
Bank Sta=4993.9,5001
Exp/Cntr=0.3,0.1

Type RM Length L Ch R = 1,7812,487,487,487
BEGIN DESCRIPTION:
Stream0346 15.0
END DESCRIPTION:
XS GIS Cut Line= 3
      1825325.00     13986724.99      1825325.00     13986225.00
      1825125.00     13985875.00
#Sta/Elev= 30
  4495.4 2123.91  4525.4 2123.78  4595.4 2118.21  4625.4 2114.31  4675.4 2109.93
  4845.4 2108.03  4975.4 2108.30  4992.9 2105.70  5009.1 2106.19  5014.9 2105.23
  5015.4 2104.73  5021.5 2104.73  5022.0 2105.23  5024.9 2106.41  5040.7 2106.48
  5046.5 2107.61  5053.0 2107.96  5070.8 2107.63  5076.0 2106.91  5099.0 2106.88
  5105.5 2108.17  5127.4 2109.07  5156.6 2110.94  5170.3 2112.46  5245.2 2126.21
  5260.3 2126.45  5294.8 2129.91  5340.9 2132.68  5375.5 2136.69  5398.5 2137.30
#Mann=5,-1,0
  4495.4    0.07       0  5014.9    0.05       0  5022.0    0.07       0
  5070.8     0.1       0  5127.4    0.07       0
Bank Sta=5014.9,5022
Exp/Cntr=0.3,0.1

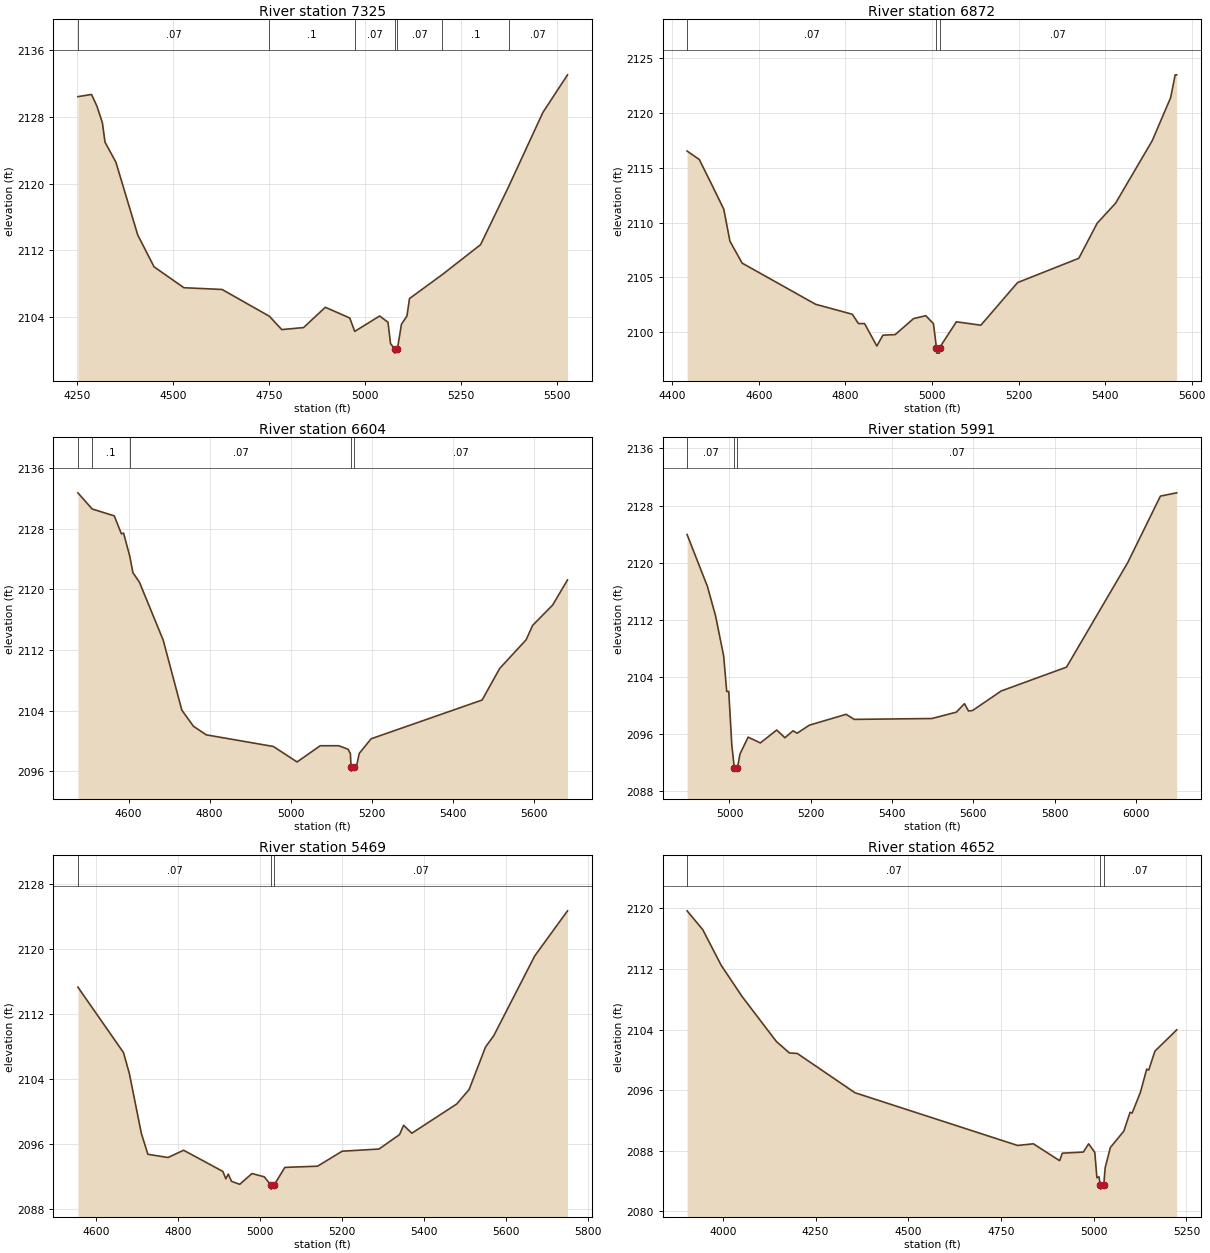
Type RM Length L Ch R = 1,7325,453,453,453
BEGIN DESCRIPTION:
Stream0346 14.0
END DESCRIPTION:
XS GIS Cut Line= 3
      1826324.99     13986624.99      1825775.00     13986125.00
      1825375.00     13985775.00
#Sta/Elev= 30
  4252.2 2130.45  4287.7 2130.71  4301.9 2129.29  4316.0 2127.31  4322.8 2124.98
  4351.2 2122.57  4407.9 2113.84  4450.5 2110.00  4528.2 2107.49  4627.6 2107.28
  4750.8 2104.06  4783.0 2102.46  4839.7 2102.70  4896.5 2105.14  4960.0 2103.85
  4973.0 2102.24  5037.7 2104.09  5059.6 2103.34  5066.2 2100.78  5076.9 2100.13
  5077.4 2099.63  5084.0 2100.13  5094.7 2103.11  5108.9 2104.08  5115.6 2106.19
  5200.2 2109.04  5300.6 2112.66  5373.9 2119.66  5462.9 2128.55  5527.0 2133.07
#Mann=7,-1,0
  4252.2    0.07       0  4750.8     0.1       0  4973.0    0.07       0
  5076.9    0.05       0  5084.0    0.07       0  5200.2     0.1       0
  5373.9    0.07       0
Bank Sta=5076.9,5084
Exp/Cntr=0.3,0.1

Type RM Length L Ch R = 1,6872,268,268,268
BEGIN DESCRIPTION:
Stream0346 13.0
END DESCRIPTION:
XS GIS Cut Line= 3
      1826524.98     13986324.98      1826125.00     13985925.00
      1825725.03     13985525.03
#Sta/Elev= 30
  4434.2 2116.53  4462.4 2115.76  4490.7 2113.51  4519.0 2111.22  4533.2 2108.30
  4561.4 2106.30  4731.1 2102.54  4816.0 2101.63  4830.1 2100.78  4844.3 2100.78
  4872.6 2098.73  4886.7 2099.72  4915.0 2099.77  4957.4 2101.23  4985.7 2101.50
  5003.4 2100.77  5010.4 2098.58  5010.9 2098.08  5017.1 2098.08  5017.6 2098.58
  5056.4 2100.94  5113.0 2100.63  5197.8 2104.52  5339.3 2106.74  5381.7 2109.94
  5424.1 2111.76  5509.0 2117.48  5551.4 2121.40  5562.0 2123.49  5565.5 2123.49
#Mann=3,-1,0
  4434.2    0.07       0  5010.4    0.05       0  5017.6    0.07       0
Bank Sta=5010.4,5017.6
Exp/Cntr=0.3,0.1

Type RM Length L Ch R = 1,6604,613,613,613
BEGIN DESCRIPTION:
Mapping XS d7469de2
END DESCRIPTION:
XS GIS Cut Line= 3
      1826823.25     13986026.50      1826438.35     13985851.10
      1825750.95     13985470.32
#Sta/Elev= 30
  4474.7 2132.75  4509.9 2130.62  4564.5 2129.71  4582.0 2127.35  4587.5 2127.43
  4602.8 2124.38  4610.5 2122.22  4626.6 2120.96  4685.2 2113.33  4731.3 2104.08
  4759.8 2101.96  4791.5 2100.82  4957.4 2099.28  5015.8 2097.24  5073.0 2099.38
  5118.7 2099.38  5141.6 2098.92  5147.4 2098.36  5149.2 2096.53  5149.7 2096.03
  5157.1 2096.53  5163.5 2096.89  5169.2 2098.36  5198.7 2100.30  5472.6 2105.41
  5516.1 2109.58  5581.3 2113.36  5597.4 2115.26  5646.6 2117.93  5683.5 2121.26
#Mann=5,-1,0
  4474.7    0.07       0  4509.9     0.1       0  4602.8    0.07       0
  5149.2    0.05       0  5157.1    0.07       0
Bank Sta=5149.2,5157.1
Exp/Cntr=0.3,0.1

Type RM Length L Ch R = 1,5991,522,522,522
BEGIN DESCRIPTION:
Stream0346 12.0
END DESCRIPTION:
XS GIS Cut Line= 3
      1826875.01     13985475.00      1826775.00     13985475.00
      1825675.04     13985375.00
#Sta/Elev= 30
  4895.7 2123.94  4945.7 2116.67  4965.7 2112.56  4985.7 2106.92  4993.2 2101.95
  4998.2 2101.95  5005.7 2094.46  5011.8 2091.29  5012.3 2090.79  5019.7 2091.29
  5025.8 2093.19  5045.9 2095.55  5076.0 2094.74  5116.2 2096.55  5136.3 2095.47
  5156.4 2096.44  5166.4 2096.10  5196.5 2097.23  5286.9 2098.75  5307.0 2098.04
  5497.8 2098.16  5558.0 2099.05  5578.1 2100.24  5588.1 2099.21  5598.2 2099.29
  5668.5 2102.02  5829.1 2105.36  5979.7 2120.00  6060.1 2129.32  6100.2 2129.78
#Mann=3,-1,0
  4895.7    0.07       0  5011.8    0.05       0  5019.7    0.07       0
Bank Sta=5011.8,5019.7
Exp/Cntr=0.3,0.1

Type RM Length L Ch R = 1,5469,817,817,817
BEGIN DESCRIPTION:
Stream0346 11.0
END DESCRIPTION:
XS GIS Cut Line= 3
      1826925.01     13985225.00      1826606.03     13985049.48
      1825774.97     13985025.00
#Sta/Elev= 30
  4554.7 2115.29  4666.0 2107.25  4680.3 2104.68  4709.5 2097.34  4725.6 2094.74
  4774.9 2094.35  4812.8 2095.24  4908.5 2092.64  4916.0 2091.73  4921.8 2092.31
  4929.8 2091.42  4949.8 2091.05  4979.8 2092.38  5009.9 2091.97  5025.9 2090.96
  5026.4 2090.46  5033.9 2090.96  5059.9 2093.13  5139.9 2093.28  5199.9 2095.12
  5290.0 2095.39  5340.0 2097.16  5350.0 2098.31  5370.0 2097.33  5480.1 2100.94
  5510.1 2102.72  5550.1 2107.94  5570.1 2109.32  5670.1 2119.12  5750.2 2124.67
#Mann=3,-1,0
  4554.7    0.07       0  5025.9    0.05       0  5033.9    0.07       0
Bank Sta=5025.9,5033.9
Exp/Cntr=0.3,0.1

Type RM Length L Ch R = 1,4652,460,460,460
BEGIN DESCRIPTION:
Stream0346 10.0
END DESCRIPTION:
XS GIS Cut Line= 3
      1827125.01     13985075.01      1826325.00     13984325.00
      1826125.01     13984225.00
#Sta/Elev= 30
  3903.5 2119.69  3945.8 2117.20  3995.6 2112.48  4052.2 2108.34  4144.1 2102.43
  4179.3 2100.91  4200.7 2100.84  4356.1 2095.65  4794.7 2088.68  4837.2 2088.90
  4908.0 2086.67  4915.3 2087.66  4972.0 2087.81  4986.2 2088.90  5002.9 2087.76
  5008.5 2084.42  5014.1 2084.54  5018.0 2083.41  5018.5 2082.91  5026.9 2083.41
  5030.8 2085.74  5044.8 2088.41  5081.2 2090.58  5097.9 2093.06  5103.5 2092.96
  5125.9 2095.71  5142.7 2098.76  5148.2 2098.64  5165.0 2101.15  5223.7 2103.96
#Mann=3,-1,0
  3903.5    0.07       0  5018.0    0.05       0  5026.9    0.07       0
Bank Sta=5018,5026.9
Exp/Cntr=0.3,0.1

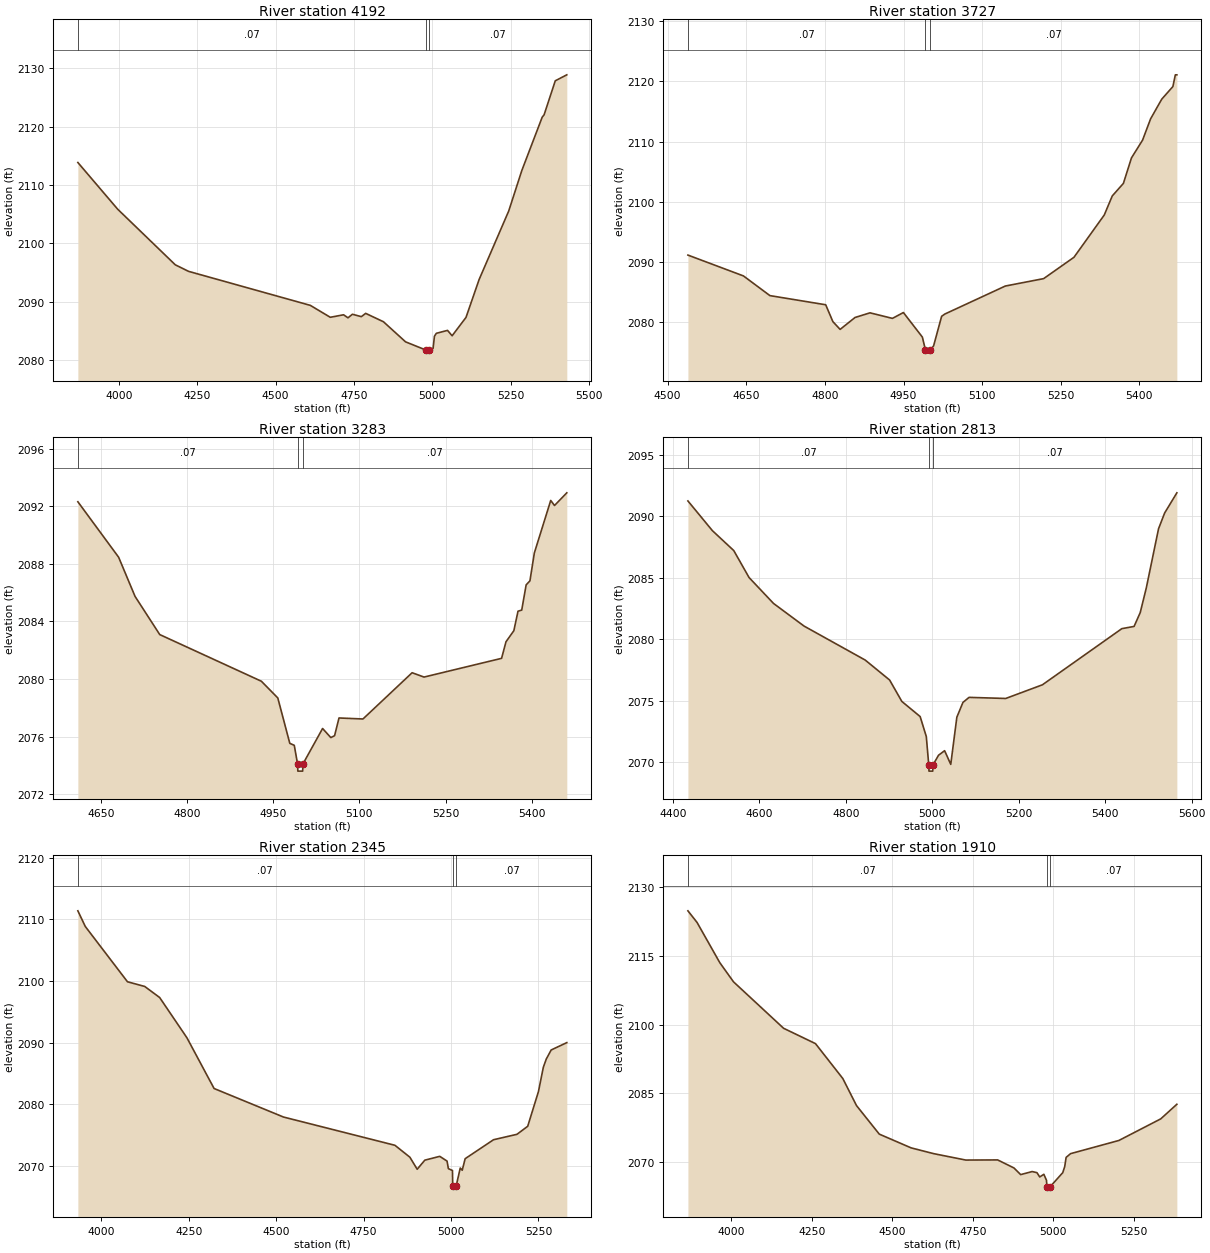
Type RM Length L Ch R = 1,4192,465,465,465
BEGIN DESCRIPTION:
Stream0346 9.0
END DESCRIPTION:
XS GIS Cut Line= 3
      1827274.97     13984724.97      1826475.00     13983925.00
      1826125.03     13983675.02
#Sta/Elev= 30
  3868.4 2113.84  3995.6 2105.85  4179.5 2096.34  4221.9 2095.22  4610.8 2089.40
  4674.5 2087.36  4716.9 2087.79  4731.0 2087.27  4745.2 2087.88  4773.5 2087.47
  4787.6 2088.03  4844.2 2086.60  4914.9 2083.16  4981.1 2081.73  4981.6 2081.23
  4989.6 2081.23  4990.1 2081.73  5002.8 2082.04  5007.1 2084.12  5013.2 2084.62
  5048.9 2085.12  5063.6 2084.20  5107.9 2087.34  5149.7 2093.81  5244.3 2105.54
  5286.1 2112.46  5351.2 2121.59  5357.3 2122.00  5393.0 2127.82  5429.8 2128.84
#Mann=3,-1,0
  3868.4    0.07       0  4981.1    0.05       0  4990.1    0.07       0
Bank Sta=4981.1,4990.1
Exp/Cntr=0.3,0.1

Type RM Length L Ch R = 1,3727,444,444,444
BEGIN DESCRIPTION:
Stream0346 8.0
END DESCRIPTION:
XS GIS Cut Line= 3
      1827074.97     13983974.97      1826775.00     13983625.00
      1826375.03     13983375.02
#Sta/Elev= 30
  4538.8 2091.15  4644.7 2087.69  4695.2 2084.42  4801.6 2082.90  4815.3 2080.10
  4829.1 2078.81  4857.6 2080.79  4886.1 2081.56  4928.9 2080.64  4949.8 2081.61
  4986.0 2077.53  4991.9 2075.37  4992.4 2074.87  5000.9 2075.37  5007.4 2076.07
  5022.7 2080.98  5028.6 2081.35  5144.2 2086.01  5217.3 2087.24  5275.1 2090.78
  5332.9 2097.80  5348.2 2100.97  5369.4 2103.05  5384.8 2107.28  5406.0 2110.24
  5421.3 2113.77  5442.5 2117.03  5463.8 2119.13  5468.5 2121.08  5471.4 2121.08
#Mann=3,-1,0
  4538.8    0.07       0  4991.9    0.05       0  5000.9    0.07       0
Bank Sta=4991.9,5000.9
Exp/Cntr=0.3,0.1

Type RM Length L Ch R = 1,3283,470,470,470
BEGIN DESCRIPTION:
Stream0346 7.0
END DESCRIPTION:
XS GIS Cut Line= 3
      1827425.02     13983625.02      1827125.00     13983375.00
      1826775.02     13983075.01
#Sta/Elev= 30
  4609.7 2092.31  4680.7 2088.46  4709.3 2085.74  4752.3 2083.09  4929.3 2079.85
  4957.9 2078.69  4978.8 2075.54  4986.6 2075.40  4992.3 2074.11  4992.8 2073.61
  5001.2 2073.61  5001.7 2074.11  5035.9 2076.57  5050.2 2075.94  5056.8 2076.07
  5064.5 2077.30  5106.2 2077.23  5191.8 2080.44  5212.6 2080.14  5347.6 2081.44
  5355.3 2082.59  5369.0 2083.36  5376.2 2084.71  5382.7 2084.79  5390.4 2086.54
  5397.0 2086.82  5404.7 2088.76  5433.2 2092.40  5439.8 2092.05  5461.2 2092.93
#Mann=3,-1,0
  4609.7    0.07       0  4992.3    0.05       0  5001.7    0.07       0
Bank Sta=4992.3,5001.7
Exp/Cntr=0.3,0.1

Type RM Length L Ch R = 1,2813,468,468,468
BEGIN DESCRIPTION:
Stream0346 6.0
END DESCRIPTION:
XS GIS Cut Line= 3
      1827725.03     13983375.03      1827325.00     13982975.00
      1826925.01     13982575.01
#Sta/Elev= 30
  4434.4 2091.23  4491.0 2088.82  4540.5 2087.20  4575.9 2085.01  4632.4 2082.91
  4703.1 2081.07  4844.6 2078.31  4901.1 2076.69  4929.4 2074.95  4971.8 2073.72
  4986.0 2072.10  4991.7 2069.79  4992.2 2069.29  5000.9 2069.29  5001.4 2069.79
  5014.3 2070.58  5028.4 2070.95  5042.6 2069.84  5056.7 2073.67  5070.8 2074.87
  5085.0 2075.28  5169.8 2075.19  5254.7 2076.30  5438.5 2080.86  5466.8 2081.04
  5481.0 2082.16  5495.1 2084.17  5523.4 2088.97  5537.5 2090.25  5565.8 2091.89
#Mann=3,-1,0
  4434.4    0.07       0  4991.7    0.05       0  5001.4    0.07       0
Bank Sta=4991.7,5001.4
Exp/Cntr=0.3,0.1

Type RM Length L Ch R = 1,2345,435,435,435
BEGIN DESCRIPTION:
Stream0346 5.0
END DESCRIPTION:
XS GIS Cut Line= 3
      1828174.99     13983224.99      1827375.00     13982525.00
      1827075.01     13982375.00
#Sta/Elev= 30
  3932.8 2111.37  3954.1 2108.83  4074.7 2099.88  4124.0 2099.12  4166.7 2097.33
  4244.6 2090.82  4322.4 2082.59  4520.8 2077.97  4839.7 2073.39  4882.4 2071.46
  4903.3 2069.51  4925.1 2070.98  4967.8 2071.60  4988.7 2070.83  4992.5 2069.61
  5004.2 2069.30  5004.9 2066.79  5005.4 2066.29  5014.7 2066.79  5026.5 2069.71
  5032.1 2069.35  5040.5 2071.22  5121.6 2074.29  5188.7 2075.17  5219.4 2076.47
  5250.1 2082.09  5264.1 2086.03  5272.5 2087.36  5286.5 2088.83  5331.2 2090.02
#Mann=3,-1,0
  3932.8    0.07       0  5004.9    0.05       0  5014.7    0.07       0
Bank Sta=5004.9,5014.7
Exp/Cntr=0.3,0.1

Type RM Length L Ch R = 1,1910,502,502,502
BEGIN DESCRIPTION:
Stream0346 4.0
END DESCRIPTION:
XS GIS Cut Line= 4
      1828425.02     13982975.02      1827762.95     13982312.95
      1827566.92     13982175.00      1827225.04     13982175.00
#Sta/Elev= 30
  3865.7 2124.87  3894.0 2122.34  3964.7 2113.54  4007.2 2109.36  4162.7 2099.21
  4261.7 2095.86  4346.6 2088.23  4389.0 2082.33  4459.7 2076.09  4558.7 2073.08
  4629.4 2071.81  4728.4 2070.42  4827.3 2070.45  4877.8 2068.70  4898.7 2067.24
  4934.4 2067.91  4949.2 2067.67  4957.9 2066.73  4970.7 2067.31  4978.9 2065.99
  4980.1 2064.57  4980.6 2064.07  4989.9 2064.57  5029.4 2067.67  5035.5 2069.01
  5039.8 2071.00  5053.6 2071.82  5203.6 2074.70  5333.6 2079.42  5383.6 2082.61
#Mann=3,-1,0
  3865.7    0.07       0  4980.1    0.05       0  4989.9    0.07       0
Bank Sta=4980.1,4989.9
Exp/Cntr=0.3,0.1

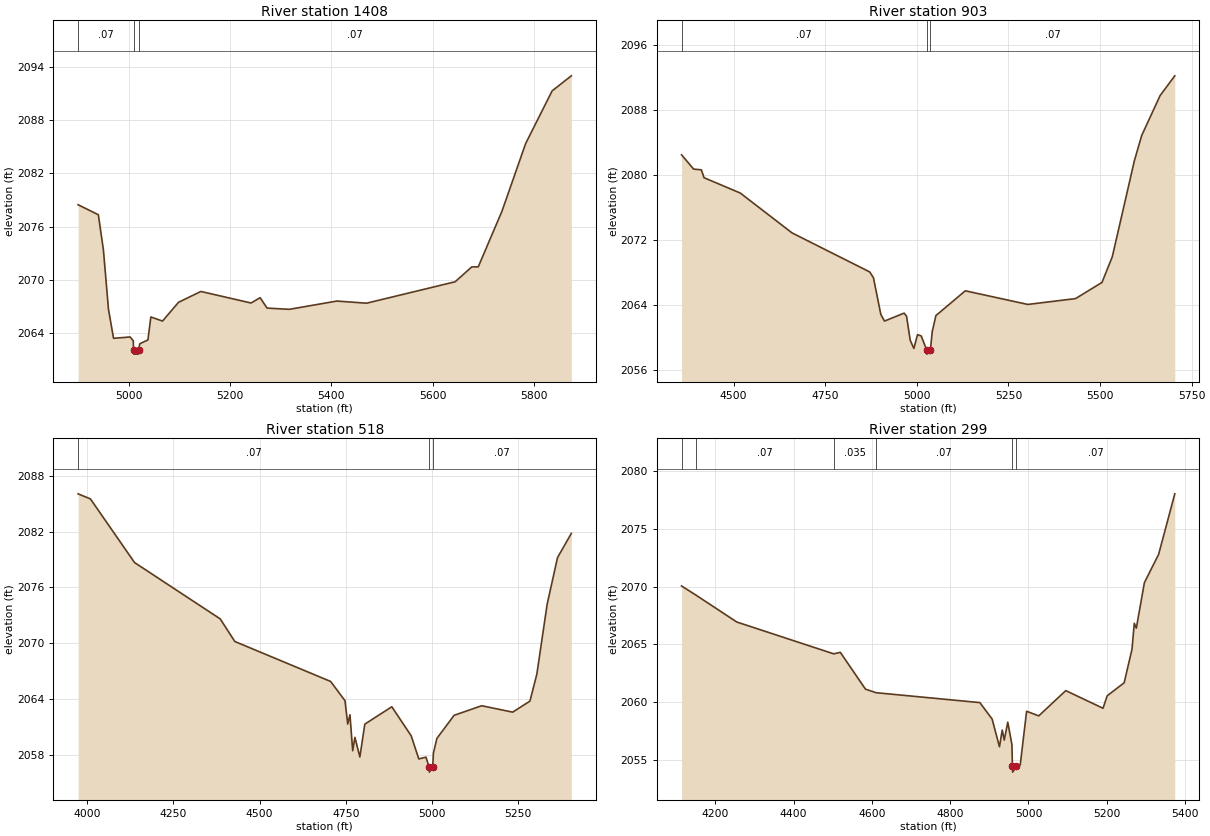
Type RM Length L Ch R = 1,1408,505,505,505
BEGIN DESCRIPTION:
Stream0346 3.0
END DESCRIPTION:
XS GIS Cut Line= 3
      1828124.98     13981975.00      1828025.00     13981975.00
      1827225.00     13981625.00
#Sta/Elev= 30
  4900.4 2078.47  4940.4 2077.34  4950.4 2073.39  4960.4 2066.70  4970.4 2063.44
  5003.1 2063.59  5009.3 2063.16  5009.9 2062.16  5010.4 2061.66  5019.3 2061.66
  5019.8 2062.16  5022.2 2062.83  5038.2 2063.25  5044.0 2065.84  5067.0 2065.38
  5098.6 2067.49  5142.7 2068.71  5241.7 2067.41  5259.6 2068.01  5273.3 2066.84
  5317.3 2066.70  5410.9 2067.63  5469.7 2067.39  5644.4 2069.80  5677.1 2071.47
  5690.0 2071.48  5736.8 2077.74  5783.5 2085.35  5835.8 2091.28  5873.6 2092.97
#Mann=3,-1,0
  4900.4    0.07       0  5009.9    0.05       0  5019.8    0.07       0
Bank Sta=5009.9,5019.8
Exp/Cntr=0.3,0.1

Type RM Length L Ch R = 1,903,385,385,385
BEGIN DESCRIPTION:
Stream0346 2.0
END DESCRIPTION:
XS GIS Cut Line= 3
      1828491.20     13981855.33      1828167.68     13981541.51
      1827274.97     13981475.00
#Sta/Elev= 30
  4358.1 2082.51  4391.1 2080.75  4412.2 2080.66  4419.4 2079.69  4518.4 2077.80
  4659.6 2072.89  4871.7 2068.08  4881.7 2067.37  4901.8 2062.86  4911.8 2062.03
  4965.3 2063.01  4972.0 2062.64  4982.0 2059.67  4992.0 2058.66  5002.0 2060.36
  5012.1 2060.20  5027.1 2058.46  5027.6 2057.96  5037.1 2058.46  5042.1 2060.73
  5052.2 2062.71  5132.4 2065.76  5302.9 2064.08  5433.2 2064.80  5505.3 2066.79
  5533.5 2069.96  5593.7 2081.78  5613.7 2084.89  5663.9 2089.81  5704.0 2092.24
#Mann=3,-1,0
  4358.1    0.07       0  5027.1    0.05       0  5037.1    0.07       0
Bank Sta=5027.1,5037.1
Exp/Cntr=0.3,0.1

Type RM Length L Ch R = 1,518,219,219,219
BEGIN DESCRIPTION:
Stream0346 1.0
END DESCRIPTION:
XS GIS Cut Line= 3
      1828674.99     13981825.00      1827875.00     13981175.00
      1827474.97     13981175.00
#Sta/Elev= 30
  3973.6 2086.07  4009.5 2085.52  4137.4 2078.68  4385.9 2072.62  4428.3 2070.19
  4706.3 2065.89  4747.9 2063.82  4755.8 2061.31  4762.3 2062.31  4770.2 2058.44
  4776.7 2059.88  4791.0 2057.77  4805.4 2061.30  4883.7 2063.17  4939.9 2060.05
  4962.0 2057.56  4982.8 2057.75  4992.2 2056.64  4992.7 2056.14  5002.2 2056.64
  5004.4 2058.18  5014.4 2059.76  5064.4 2062.25  5144.4 2063.28  5234.4 2062.59
  5284.4 2063.78  5304.4 2066.67  5334.4 2074.21  5364.4 2079.21  5404.4 2081.81
#Mann=3,-1,0
  3973.6    0.07       0  4992.2    0.05       0  5002.2    0.07       0
Bank Sta=4992.2,5002.2
Exp/Cntr=0.3,0.1

Type RM Length L Ch R = 1,299,0,0,0
BEGIN DESCRIPTION:
Stream0346 0.0
END DESCRIPTION:
XS GIS Cut Line= 3
      1828655.11     13981260.07      1828084.56     13980918.92
      1827521.67     13981113.70
#Sta/Elev= 30
  4113.5 2070.07  4150.4 2069.27  4254.7 2066.94  4502.3 2064.18  4519.2 2064.31
  4583.4 2061.12  4610.4 2060.81  4875.8 2059.95  4907.0 2058.53  4925.9 2056.12
  4932.9 2057.57  4938.1 2056.70  4947.1 2058.25  4957.7 2056.31  4959.0 2054.42
  4959.5 2053.92  4969.0 2054.42  4978.9 2054.54  4995.2 2059.20  5026.3 2058.80
  5095.3 2060.99  5190.5 2059.46  5201.1 2060.54  5244.5 2061.67  5264.6 2064.59
  5270.4 2066.83  5275.6 2066.41  5296.2 2070.35  5332.7 2072.82  5373.9 2078.06
#Mann=6,-1,0
  4113.5     0.1       0  4150.4    0.07       0  4502.3   0.035       0
  4610.4    0.07       0  4959.0    0.05       0  4969.0    0.07       0
Bank Sta=4959,4969
Exp/Cntr=0.3,0.1

Chan Stop Cuts=-1