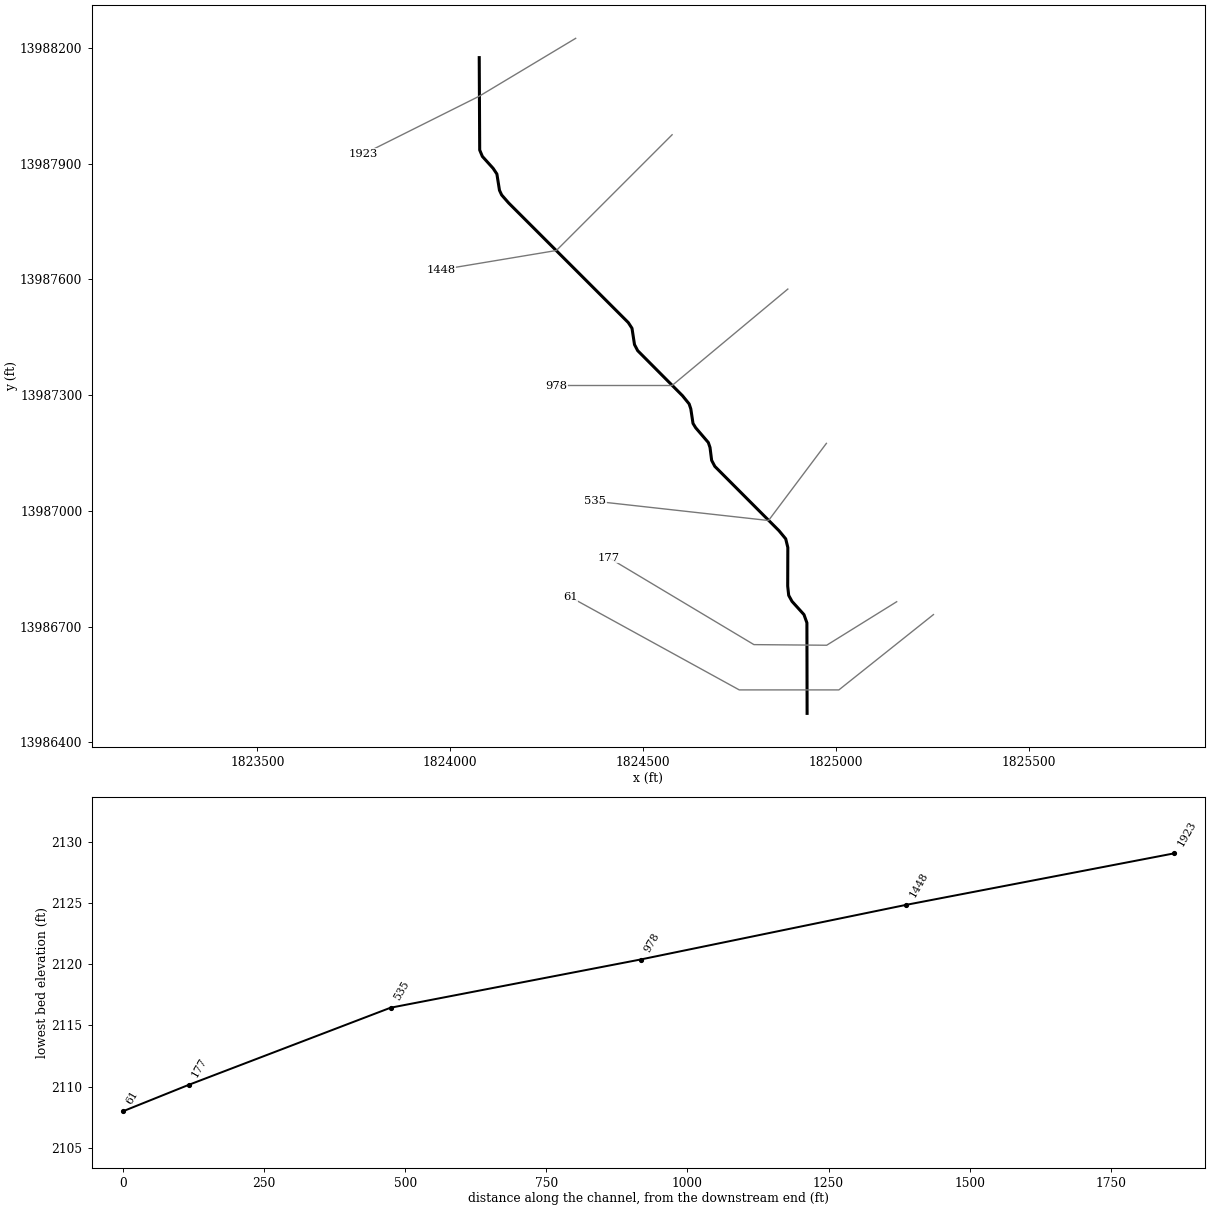
--- Stream0347.prj (project) ---

Proj Title=Stream0347 Base Level Engineering
Current Plan=p01
Default Exp/Contr=0.3,0.1
English Units
Geom File=g01
Flow File=f01
Plan File=p01
Y Axis Title=Elevation
X Axis Title(PF)=Main Channel Distance
X Axis Title(XS)=Station
BEGIN DESCRIPTION:
Stream0347
END DESCRIPTION:
DSS Export Rating Curves= 0
DSS Export Rating Curve Sorted= 0
DSS Export Volume Flow Curves= 0
DXF OffsetX= 0
DXF OffsetY= 0
DXF ScaleX= 1
DXF ScaleY= 10

--- Stream0347.p01 (plan) ---

Plan Title=Multiple Run
Short Identifier=Multiple
Geom File=g01
Flow File=f01
Subcritical Flow
K Sum by GR= 0
Std Step Tol= 0.01
Critical Tol= 0.01
Num of Std Step Trials= 20
Max Error Tol= 0.3
Flow Tol Ratio= 0.001
Split Flow NTrial= 30
Split Flow Tol= 0.02
Split Flow Ratio= 0.02
Log Output Level= 0
Friction Slope Method= 1
Unsteady Friction Slope Method= 2
Unsteady Bridges Friction Slope Method= 1
Parabolic Critical Depth
Global Vel Dist=  1 , 1 , 1
Global Log Level= 0
CheckData=True
Encroach Param= -1, 0, 0, 0
BEGIN DESCRIPTION:
Multiple Run
END DESCRIPTION:

--- Stream0347.f01 (steady flow) ---

Flow Title=Multiple
Program Version=4.10
Number of Profiles= 7
Profile Names=10-year,25-year,50-year,1pct_min,100-year,1pct_plu,500-year
River Rch & RM=Stream0347,Reach-1         ,1923
     969    1633    2255    1504    3002    5989    5256
Boundary for River Rch & Prof#=Stream0347,Reach-1         , 1
Up Type= 0
Dn Type= 3
Dn Slope=0.01
Boundary for River Rch & Prof#=Stream0347,Reach-1         , 2
Up Type= 0
Dn Type= 3
Dn Slope=0.01
Boundary for River Rch & Prof#=Stream0347,Reach-1         , 3
Up Type= 0
Dn Type= 3
Dn Slope=0.01
Boundary for River Rch & Prof#=Stream0347,Reach-1         , 4
Up Type= 0
Dn Type= 3
Dn Slope=0.01
Boundary for River Rch & Prof#=Stream0347,Reach-1         , 5
Up Type= 0
Dn Type= 3
Dn Slope=0.01
Boundary for River Rch & Prof#=Stream0347,Reach-1         , 6
Up Type= 0
Dn Type= 3
Dn Slope=0.01
Boundary for River Rch & Prof#=Stream0347,Reach-1         , 7
Up Type= 0
Dn Type= 3
Dn Slope=0.01
DSS Import GetInterval= 0
DSS Import GetPeak= 0
DSS Import FillOption= 0

--- Stream0347.g01 (geometry) ---

Geom Title=Existing Conditions
Program Version=4.10

River Reach=Stream0347      ,Reach-1
Reach XY= 30
        1824075.       13988175.       1824076.2      13987935.5
      1824083.09     13987918.92      1824110.95     13987888.03
      1824120.78     13987873.25       1824127.5     13987831.03
      1824133.14     13987818.94      1824151.29     13987798.18
      1824461.37     13987488.21      1824471.02     13987473.35
      1824477.54     13987431.05      1824485.78     13987415.32
      1824601.99     13987298.47      1824619.17      13987277.3
       1824623.5     13987264.38      1824629.19     13987226.74
       1824636.1     13987215.45       1824668.9     13987177.19
       1824673.3      13987164.3       1824677.5     13987131.04
      1824685.76     13987115.32      1824852.14     13986948.53
      1824869.53     13986927.45      1824875.02     13986905.01
      1824874.68     13986804.87      1824877.27     13986780.94
      1824885.86     13986765.36      1824916.86     13986731.06
      1824924.48     13986709.78        1824925.       13986475.

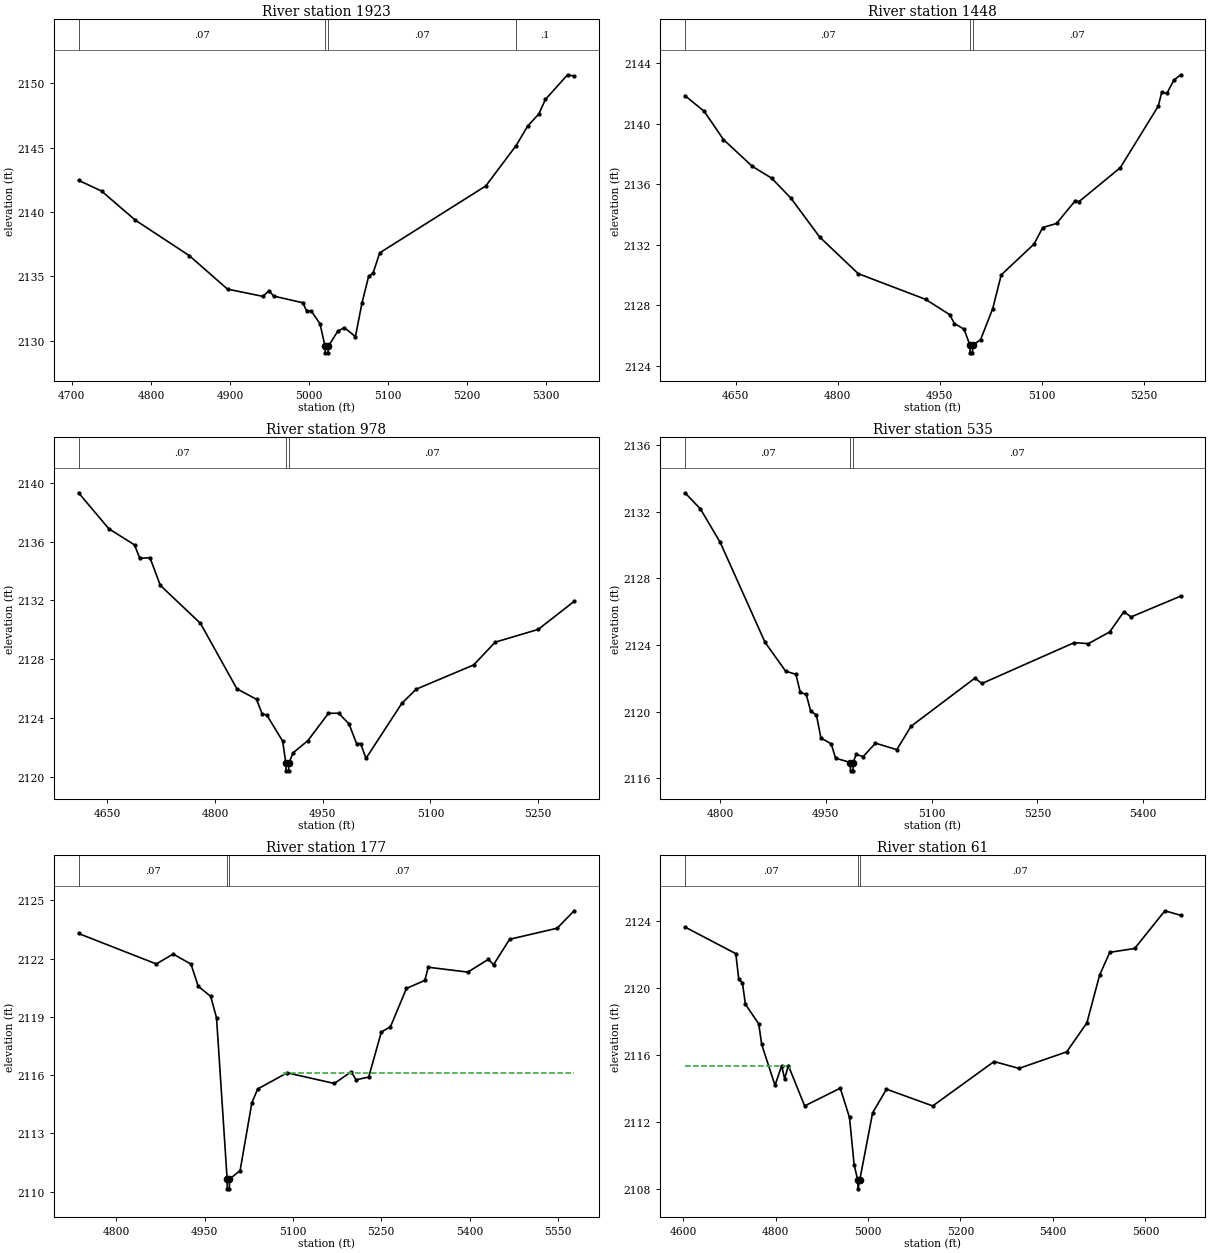
Type RM Length L Ch R = 1 ,1923    ,475,475,475
BEGIN DESCRIPTION:
Stream0347 4.0
END DESCRIPTION:
XS GIS Cut Line= 3
      1824325.01     13988225.01        1824075.       13988075.
      1823774.97     13987924.99
#Sta/Elev= 30
  4708.4 2142.47  4737.6 2141.63  4780.3 2139.37  4848.4 2136.62  4896.9 2134.01
  4941.6 2133.45  4949.4 2133.88  4955.3 2133.47  4992.2 2132.95    4997 2132.31
  5002.8 2132.31  5013.9 2131.32  5020.3 2129.56  5020.6 2129.06  5024.1 2129.06
  5024.3 2129.56  5036.3 2130.73  5044.7 2131.02  5058.7 2130.32    5067 2132.94
  5075.4    2135    5081 2135.25  5089.4 2136.83  5223.6 2142.03    5262 2145.17
  5276.7 2146.69  5290.6 2147.62    5299 2148.75    5327 2150.67  5335.4 2150.57
#Mann= 4 ,-1 , 0
  4708.4     .07       0  5020.3     .05       0  5024.3     .07       0
    5262      .1       0
Bank Sta=5020.3,5024.3
XS Rating Curve= 0 ,0
Exp/Cntr=0.3,0.1

Type RM Length L Ch R = 1 ,1448    ,470,470,470
BEGIN DESCRIPTION:
Stream0347 3.0
END DESCRIPTION:
XS GIS Cut Line= 3
      1824575.02     13987975.02        1824275.       13987675.
      1823975.03     13987625.01
#Sta/Elev= 30
  4575.7 2141.87    4604 2140.83  4632.3 2138.96  4674.7 2137.19    4703 2136.41
  4731.3 2135.09  4773.7 2132.51  4830.3 2130.09  4929.3 2128.39  4964.6 2127.38
  4971.7 2126.79  4985.9 2126.41  4994.5 2125.35  4994.7 2124.85  4998.2 2124.85
  4998.5 2125.35  5010.1 2125.72  5027.9 2127.77  5040.5 2130.01  5088.7 2132.05
  5101.4 2133.14  5121.7 2133.41  5149.5 2134.93  5154.6 2134.85  5215.4  2137.1
  5271.2 2141.17  5276.3 2142.09  5283.9 2142.02    5294 2142.88  5304.1 2143.25
#Mann= 3 ,-1 , 0
  4575.7     .07       0  4994.5     .05       0  4998.5     .07       0
Bank Sta=4994.5,4998.5
XS Rating Curve= 0 ,0
Exp/Cntr=0.3,0.1

Type RM Length L Ch R = 1 ,978     ,443,443,443
BEGIN DESCRIPTION:
Stream0347 2.0
END DESCRIPTION:
XS GIS Cut Line= 3
      1824875.01     13987575.01        1824575.       13987325.
      1824275.03       13987325.
#Sta/Elev= 30
  4609.7 2139.32    4652 2136.87  4687.8 2135.77    4695 2134.86  4709.3  2134.9
  4723.6 2133.02  4779.6 2130.43  4830.4 2125.97  4857.7 2125.26  4865.5 2124.27
    4872 2124.19  4894.1 2122.41  4898.6 2120.89  4898.9 2120.39  4902.4 2120.39
  4902.6 2120.89  4908.5 2121.61  4929.3 2122.45  4957.9 2124.31  4972.2 2124.31
  4986.6 2123.58    4997 2122.25  5002.7 2122.25  5010.2 2121.24  5060.2 2124.99
  5080.2 2125.95  5160.2  2127.6  5190.2 2129.15  5250.2 2130.02  5300.2 2131.93
#Mann= 3 ,-1 , 0
  4609.7     .07       0  4898.6     .05       0  4902.6     .07       0
Bank Sta=4898.6,4902.6
XS Rating Curve= 0 ,0
Exp/Cntr=0.3,0.1

Type RM Length L Ch R = 1 ,535     ,358,358,358
BEGIN DESCRIPTION:
Stream0347 1.0
END DESCRIPTION:
XS GIS Cut Line= 3
      1824974.99     13987174.98        1824825.       13986975.
      1824375.05     13987024.99
#Sta/Elev= 30
  4750.3 2133.13  4772.2 2132.16  4800.3 2130.15  4863.8 2124.16    4893 2122.43
  4907.6 2122.24  4913.8 2121.15  4922.2 2121.04  4928.4 2120.04  4936.7  2119.8
    4943 2118.42  4957.6 2118.07  4963.8 2117.21  4984.7 2116.95    4985 2116.45
  4988.5 2116.45  4988.7 2116.95    4993 2117.44  5002.8  2117.3  5020.4 2118.11
  5050.6 2117.72  5070.7 2119.12  5161.3 2122.01  5171.3 2121.69  5302.1 2124.14
  5322.2 2124.08  5352.4 2124.78  5372.6    2126  5382.6 2125.68    5453 2126.93
#Mann= 3 ,-1 , 0
  4750.3     .07       0  4984.7     .05       0  4988.7     .07       0
Bank Sta=4984.7,4988.7
XS Rating Curve= 0 ,0
Exp/Cntr=0.3,0.1

Type RM Length L Ch R = 1 ,177     ,116,116,116
BEGIN DESCRIPTION:
Stream0347 0.0
END DESCRIPTION:
XS GIS Cut Line= 4
      1825157.23     13986764.44      1824975.72     13986651.64
      1824787.11     13986653.26      1824410.09     13986878.89
#Sta/Elev= 30
  4735.8  2123.3  4867.9 2121.73  4896.6 2122.24  4926.8 2121.72  4939.1 2120.58
  4960.2 2120.06  4970.2 2118.95  4988.2 2110.64  4988.5 2110.14    4992 2110.14
  4992.2 2110.64  5010.2 2111.08  5030.2 2114.58  5040.2 2115.29  5090.2 2116.12
  5170.2 2115.57  5198.8 2116.17  5207.2 2115.76  5228.6  2115.9    5250 2118.22
  5265.5 2118.49  5292.7 2120.47  5323.9 2120.88  5329.7 2121.56    5397 2121.31
  5431.9 2121.97  5440.6 2121.69  5467.8    2123  5548.5 2123.57  5577.5 2124.47
#Mann= 3 ,-1 , 0
  4735.8     .07       0  4988.2     .05       0  4992.2     .07       0
#XS Ineff= 2 , 0
                          5084.5         2116.09
Permanent Ineff=
       F       F
Bank Sta=4988.2,4992.2
XS Rating Curve= 0 ,0
Exp/Cntr=0.3,0.1

Type RM Length L Ch R = 1 ,61      ,0,0,0
BEGIN DESCRIPTION:
Stream0347 0.1
END DESCRIPTION:
XS GIS Cut Line= 4
      1825252.56     13986731.13      1825007.36     13986535.84
      1824749.12     13986535.84      1824310.75     13986776.72
#Sta/Elev= 30
  4604.2 2123.62  4714.1 2122.03  4720.4 2120.53  4728.5 2120.28  4734.9 2119.01
  4763.7 2117.84  4770.1 2116.61  4798.9 2114.17  4813.3 2115.34  4819.7 2114.56
  4827.8 2115.35    4863 2112.94    4940    2114    4960 2112.25    4970 2109.43
    4978 2108.49  4978.3 2107.99    4982 2108.49    5010 2112.53    5040 2113.94
    5140 2112.94  5272.6 2115.59  5326.6 2115.18  5429.8 2116.17  5473.4  2117.9
  5500.9 2120.75  5522.9 2122.11  5576.7 2122.34    5642 2124.59  5676.1 2124.32
#Mann= 3 ,-1 , 0
  4604.2     .07       0    4978     .05       0    4982     .07       0
#XS Ineff= 2 , 0
         4831.01 2115.35 5272.87         2115.44
Permanent Ineff=
       F       F
Bank Sta=4978,4982
XS Rating Curve= 0 ,0
Exp/Cntr=0.3,0.1

Chan Stop Cuts=-1
Use User Specified Reach Order=0
Composite Channel Slope=5