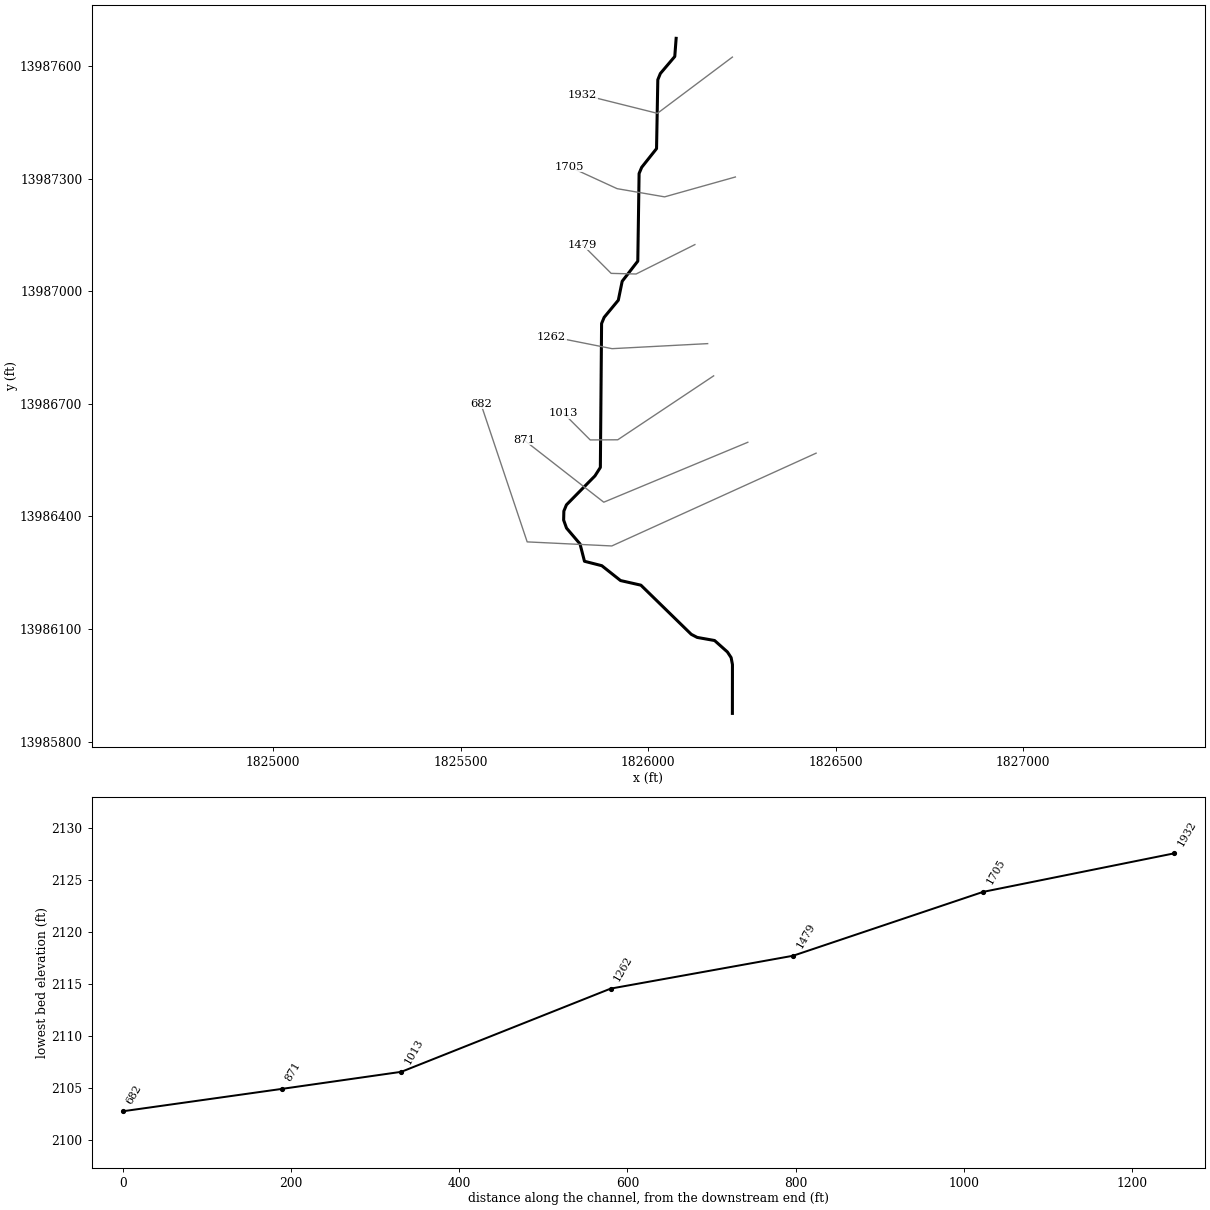
--- Stream0348.prj (project) ---

Proj Title=Stream0348 Base Level Engineering
Current Plan=p01
Default Exp/Contr=0.3,0.1
English Units
Geom File=g01
Flow File=f01
Plan File=p01
BEGIN DESCRIPTION:
Stream0348
END DESCRIPTION:

--- Stream0348.p01 (plan) ---

Plan Title=Multiple Run
Short Identifier=Multiple
Geom File=g01
Flow File=f01
Subcritical Flow
K Sum by GR= 0
Std Step Tol= 0.01
Critical Tol= 0.01
Num of Std Step Trials= 20
Max Error Tol= 0.3
Flow Tol Ratio= 0.001
Split Flow NTrial= 30
Split Flow Tol= 0.02
Split Flow Ratio= 0.02
Log Output Level= 0
Friction Slope Method= 1
Unsteady Friction Slope Method= 2
Unsteady Bridges Friction Slope Method= 1
Parabolic Critical Depth
Global Vel Dist=  1 , 1 , 1
Global Log Level= 0
CheckData=True
Encroach Param= -1, 0, 0, 0
BEGIN DESCRIPTION:
Multiple Run
END DESCRIPTION:

--- Stream0348.f01 (steady flow) ---

Flow Title=Multiple
Number of Profiles=7
Profile Names=10-year,25-year,50-year,1pct_min,100-year,1pct_plu,500-year
River Rch & RM= Stream0348,Reach-1,1932
     299     467     614     392     783    1562    1251
Boundary for River Rch & Prof#=Stream0348,Reach-1,1
Up Type=0
Dn Type=3
Dn Slope=0.005
Boundary for River Rch & Prof#=Stream0348,Reach-1,2
Up Type=0
Dn Type=3
Dn Slope=0.005
Boundary for River Rch & Prof#=Stream0348,Reach-1,3
Up Type=0
Dn Type=3
Dn Slope=0.005
Boundary for River Rch & Prof#=Stream0348,Reach-1,4
Up Type=0
Dn Type=3
Dn Slope=0.005
Boundary for River Rch & Prof#=Stream0348,Reach-1,5
Up Type=0
Dn Type=3
Dn Slope=0.005
Boundary for River Rch & Prof#=Stream0348,Reach-1,6
Up Type=0
Dn Type=3
Dn Slope=0.005
Boundary for River Rch & Prof#=Stream0348,Reach-1,7
Up Type=0
Dn Type=3
Dn Slope=0.005

--- Stream0348.g01 (geometry) ---

Geom Title=Existing Conditions

River Reach=Stream0348,Reach-1
Reach XY= 30
      1826075.00     13987675.00      1826071.35     13987626.51
      1826032.89     13987581.16      1826026.12     13987564.54
      1826022.74     13987380.94      1825983.14     13987331.06
      1825976.22     13987314.50      1825972.76     13987080.93
      1825931.12     13987027.18      1825920.81     13986976.74
      1825883.09     13986931.08      1825876.20     13986914.50
      1825872.93     13986530.86      1825858.53     13986508.25
      1825782.50     13986431.05      1825775.60     13986414.37
      1825775.01     13986390.40      1825782.73     13986369.02
      1825818.68     13986326.85      1825830.58     13986280.58
      1825876.85     13986268.76      1825926.71     13986229.18
      1825981.05     13986216.86      1826115.34     13986085.79
      1826131.09     13986077.55      1826177.57     13986069.26
      1826211.79     13986038.68      1826221.60     13986023.77
      1826225.16     13986005.16      1826225.00     13985875.00

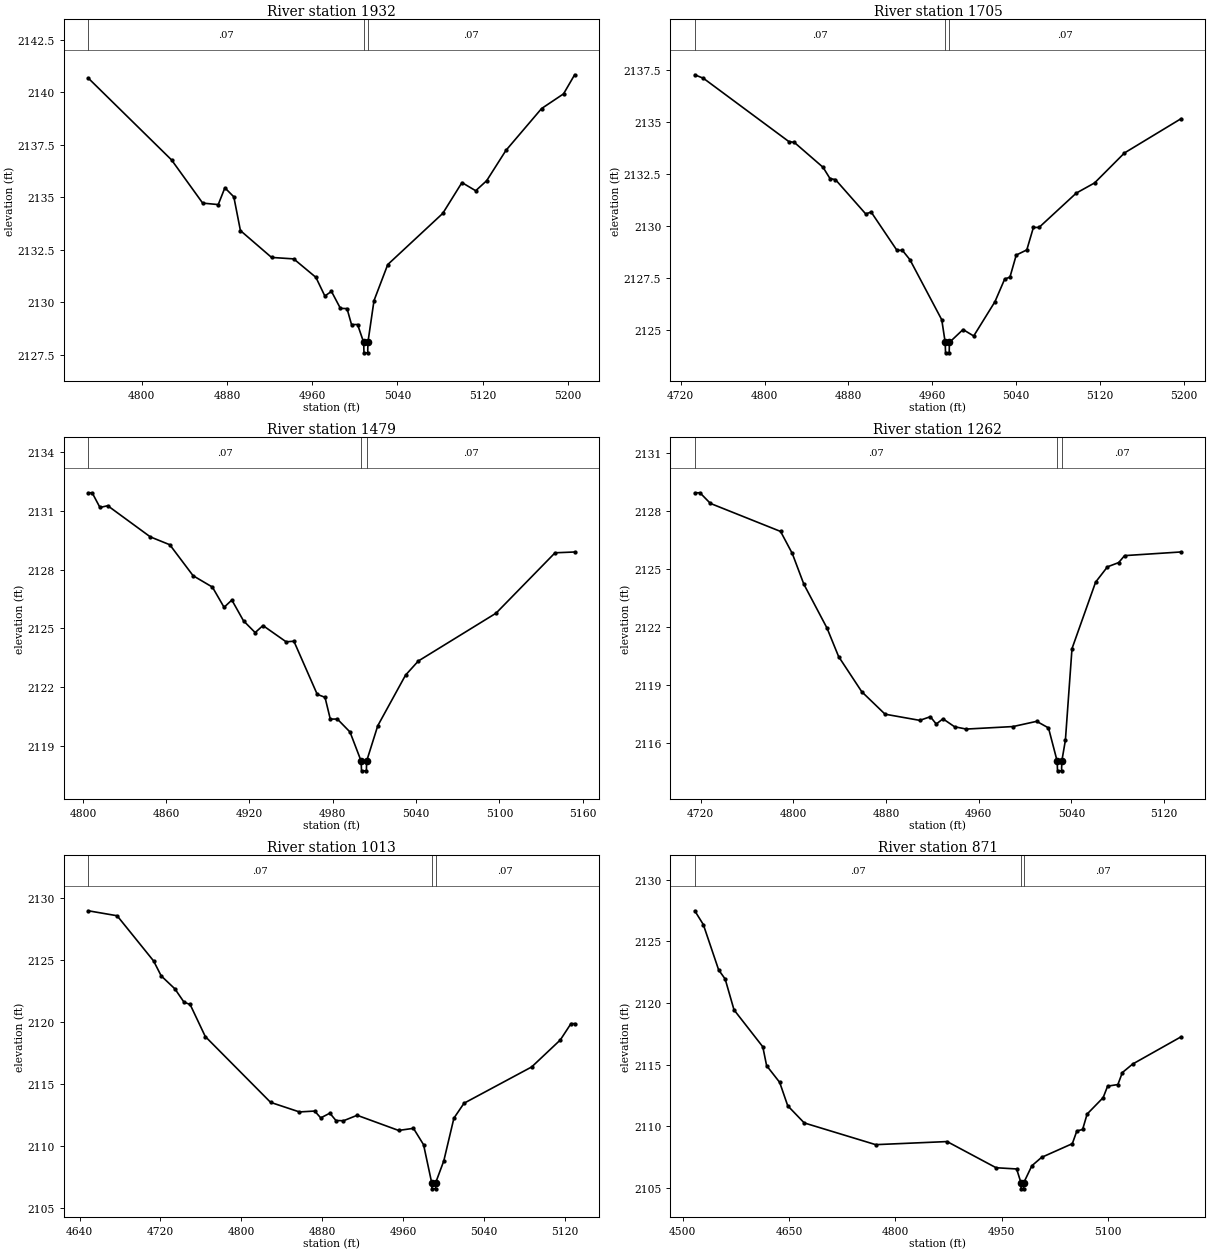
Type RM Length L Ch R = 1,1932,227,227,227
BEGIN DESCRIPTION:
Stream0348 3.0
END DESCRIPTION:
XS GIS Cut Line= 3
      1826225.00     13987625.00      1826025.00     13987475.00
      1825824.95     13987525.01
#Sta/Elev= 30
  4750.0 2140.68  4828.1 2136.78  4857.3 2134.72  4871.9 2134.65  4878.1 2135.45
  4886.5 2135.02  4892.7 2133.41  4921.9 2132.13  4942.7 2132.06  4963.5 2131.18
  4971.9 2130.29  4978.1 2130.51  4986.5 2129.70  4992.7 2129.69  4996.9 2128.93
  5002.6 2128.93  5008.3 2128.08  5008.6 2127.58  5012.1 2127.58  5012.3 2128.08
  5018.0 2130.07  5030.9 2131.79  5082.5 2134.23  5100.5 2135.70  5113.4 2135.31
  5123.7 2135.79  5141.7 2137.23  5175.2 2139.23  5195.8 2139.93  5206.2 2140.84
#Mann=3,-1,0
  4750.0    0.07       0  5008.3    0.05       0  5012.3    0.07       0
Bank Sta=5008.3,5012.3
Exp/Cntr=0.3,0.1

Type RM Length L Ch R = 1,1705,226,226,226
BEGIN DESCRIPTION:
Mapping XS 0cb6698d
END DESCRIPTION:
XS GIS Cut Line= 4
      1826232.96     13987305.28      1826044.25     13987252.29
      1825917.54     13987274.17      1825790.60     13987332.50
#Sta/Elev= 30
  4733.4 2137.25  4741.7 2137.08  4823.2 2134.04  4828.4 2134.00  4855.9 2132.80
  4862.5 2132.26  4867.7 2132.21  4896.6 2130.56  4901.8 2130.65  4926.4 2128.81
  4931.6 2128.81  4938.8 2128.36  4969.2 2125.47  4972.5 2124.38  4972.8 2123.88
  4976.3 2123.88  4976.5 2124.38  4989.5 2125.00  4999.7 2124.69  5020.0 2126.34
  5029.3 2127.43  5034.3 2127.52  5040.3 2128.58  5050.4 2128.83  5056.7 2129.91
  5062.1 2129.91  5097.6 2131.56  5115.1 2132.05  5143.6 2133.49  5197.7 2135.14
#Mann=3,-1,0
  4733.4    0.07       0  4972.5    0.05       0  4976.5    0.07       0
Bank Sta=4972.5,4976.5
Exp/Cntr=0.3,0.1

Type RM Length L Ch R = 1,1479,217,217,217
BEGIN DESCRIPTION:
Stream0348 2.0
END DESCRIPTION:
XS GIS Cut Line= 4
      1826125.00     13987125.00      1825968.20     13987046.60
      1825901.73     13987048.27      1825825.01     13987124.99
#Sta/Elev= 30
  4803.9 2131.92  4806.7 2131.92  4812.3 2131.17  4817.9 2131.26  4848.6 2129.67
  4862.6 2129.27  4879.4 2127.69  4893.3 2127.11  4901.7 2126.08  4907.3 2126.45
  4915.7 2125.39  4924.1 2124.79  4929.7 2125.15  4946.4 2124.32  4952.0 2124.35
  4968.8 2121.64  4974.4 2121.49  4978.2 2120.38  4983.3 2120.38  4992.4 2119.72
  5000.4 2118.24  5000.7 2117.74  5004.2 2117.74  5004.4 2118.24  5012.4 2120.04
  5032.4 2122.62  5041.6 2123.34  5097.6 2125.78  5140.1 2128.86  5154.2 2128.90
#Mann=3,-1,0
  4803.9    0.07       0  5000.4    0.05       0  5004.4    0.07       0
Bank Sta=5000.4,5004.4
Exp/Cntr=0.3,0.1

Type RM Length L Ch R = 1,1262,249,249,249
BEGIN DESCRIPTION:
Mapping XS 70014a57
END DESCRIPTION:
XS GIS Cut Line= 3
      1826159.04     13986860.95      1825904.15     13986847.49
      1825742.66     13986879.61
#Sta/Elev= 30
  4714.8 2128.96  4719.3 2128.96  4728.3 2128.41  4788.9 2126.96  4799.0 2125.82
  4809.0 2124.23  4829.0 2121.96  4839.0 2120.49  4859.0 2118.67  4879.1 2117.51
  4909.1 2117.19  4918.2 2117.38  4923.3 2117.00  4929.1 2117.27  4939.1 2116.86
  4949.2 2116.74  4989.6 2116.87  5010.0 2117.14  5020.2 2116.80  5027.7 2115.08
  5028.0 2114.58  5031.5 2114.58  5031.7 2115.08  5034.8 2116.16  5040.5 2120.90
  5060.9 2124.34  5071.1 2125.13  5080.8 2125.35  5085.9 2125.71  5134.7 2125.90
#Mann=3,-1,0
  4714.8    0.07       0  5027.7    0.05       0  5031.7    0.07       0
Bank Sta=5027.7,5031.7
Exp/Cntr=0.3,0.1

Type RM Length L Ch R = 1,1013,142,142,142
BEGIN DESCRIPTION:
Stream0348 1.0
END DESCRIPTION:
XS GIS Cut Line= 4
      1826175.00     13986775.00      1825919.30     13986604.53
      1825845.85     13986604.15      1825774.98     13986675.02
#Sta/Elev= 30
  4648.6 2128.96  4677.1 2128.56  4713.2 2124.92  4720.7 2123.72  4734.2 2122.68
  4743.3 2121.60  4749.3 2121.42  4764.3 2118.84  4828.9 2113.54  4857.4 2112.77
  4872.5 2112.84  4878.5 2112.29  4887.5 2112.67  4893.5 2112.08  4901.0 2112.06
  4914.5 2112.50  4955.5 2111.28  4970.2 2111.45  4980.2 2110.13  4988.2 2107.08
  4988.5 2106.58  4992.0 2106.58  4992.2 2107.08  5000.2 2108.83  5010.2 2112.27
  5020.2 2113.47  5087.1 2116.39  5115.4 2118.56  5126.0 2119.88  5129.6 2119.88
#Mann=3,-1,0
  4648.6    0.07       0  4988.2    0.05       0  4992.2    0.07       0
Bank Sta=4988.2,4992.2
Exp/Cntr=0.3,0.1

Type RM Length L Ch R = 1,871,189,189,189
BEGIN DESCRIPTION:
Stream0348 0.0
END DESCRIPTION:
XS GIS Cut Line= 3
      1826266.14     13986597.90      1825882.00     13986438.10
      1825668.94     13986604.33
#Sta/Elev= 30
  4517.1 2127.47  4529.2 2126.35  4550.8 2122.68  4560.0 2121.94  4572.5 2119.44
  4613.1 2116.45  4618.5 2114.92  4636.9 2113.57  4648.3 2111.67  4671.6 2110.28
  4772.4 2108.52  4873.2 2108.77  4942.3 2106.65  4971.3 2106.55  4977.4 2105.44
  4977.6 2104.94  4981.1 2104.94  4981.4 2105.44  4992.8 2106.81  5006.5 2107.49
  5049.9 2108.60  5056.3 2109.63  5064.4 2109.75  5070.8 2111.00  5093.4 2112.33
  5099.7 2113.26  5114.2 2113.39  5120.5 2114.36  5135.0 2115.05  5203.4 2117.26
#Mann=3,-1,0
  4517.1    0.07       0  4977.4    0.05       0  4981.4    0.07       0
Bank Sta=4977.4,4981.4
Exp/Cntr=0.3,0.1

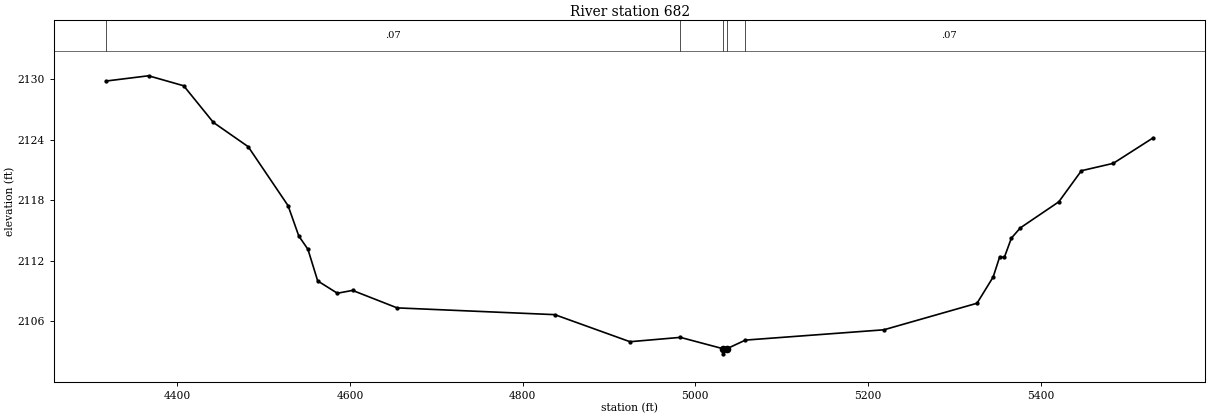
Type RM Length L Ch R = 1,682,0,0,0
BEGIN DESCRIPTION:
Stream0348 T
END DESCRIPTION:
XS GIS Cut Line= 4
      1826448.20     13986568.84      1825903.48     13986321.44
      1825677.79     13986332.29      1825554.29     13986700.62
#Sta/Elev= 30
  4317.5 2129.80  4366.7 2130.32  4407.4 2129.33  4441.8 2125.70  4482.1 2123.30
  4528.3 2117.46  4540.7 2114.46  4551.3 2113.14  4562.6 2110.01  4585.4 2108.79
  4603.0 2109.07  4654.6 2107.34  4837.2 2106.67  4924.3 2103.99  4982.7 2104.42
  5032.4 2103.29  5032.6 2102.79  5036.4 2103.29  5058.0 2104.15  5218.4 2105.17
  5326.3 2107.80  5345.0 2110.40  5352.6 2112.41  5357.9 2112.33  5366.1 2114.25
  5376.6 2115.27  5421.0 2117.84  5447.2 2120.92  5484.1 2121.65  5530.2 2124.17
#Mann=5,-1,0
  4317.5    0.07       0  4982.7     0.1       0  5032.4    0.05       0
  5036.4     0.1       0  5058.0    0.07       0
Bank Sta=5032.4,5036.4
Exp/Cntr=0.3,0.1

Chan Stop Cuts=-1