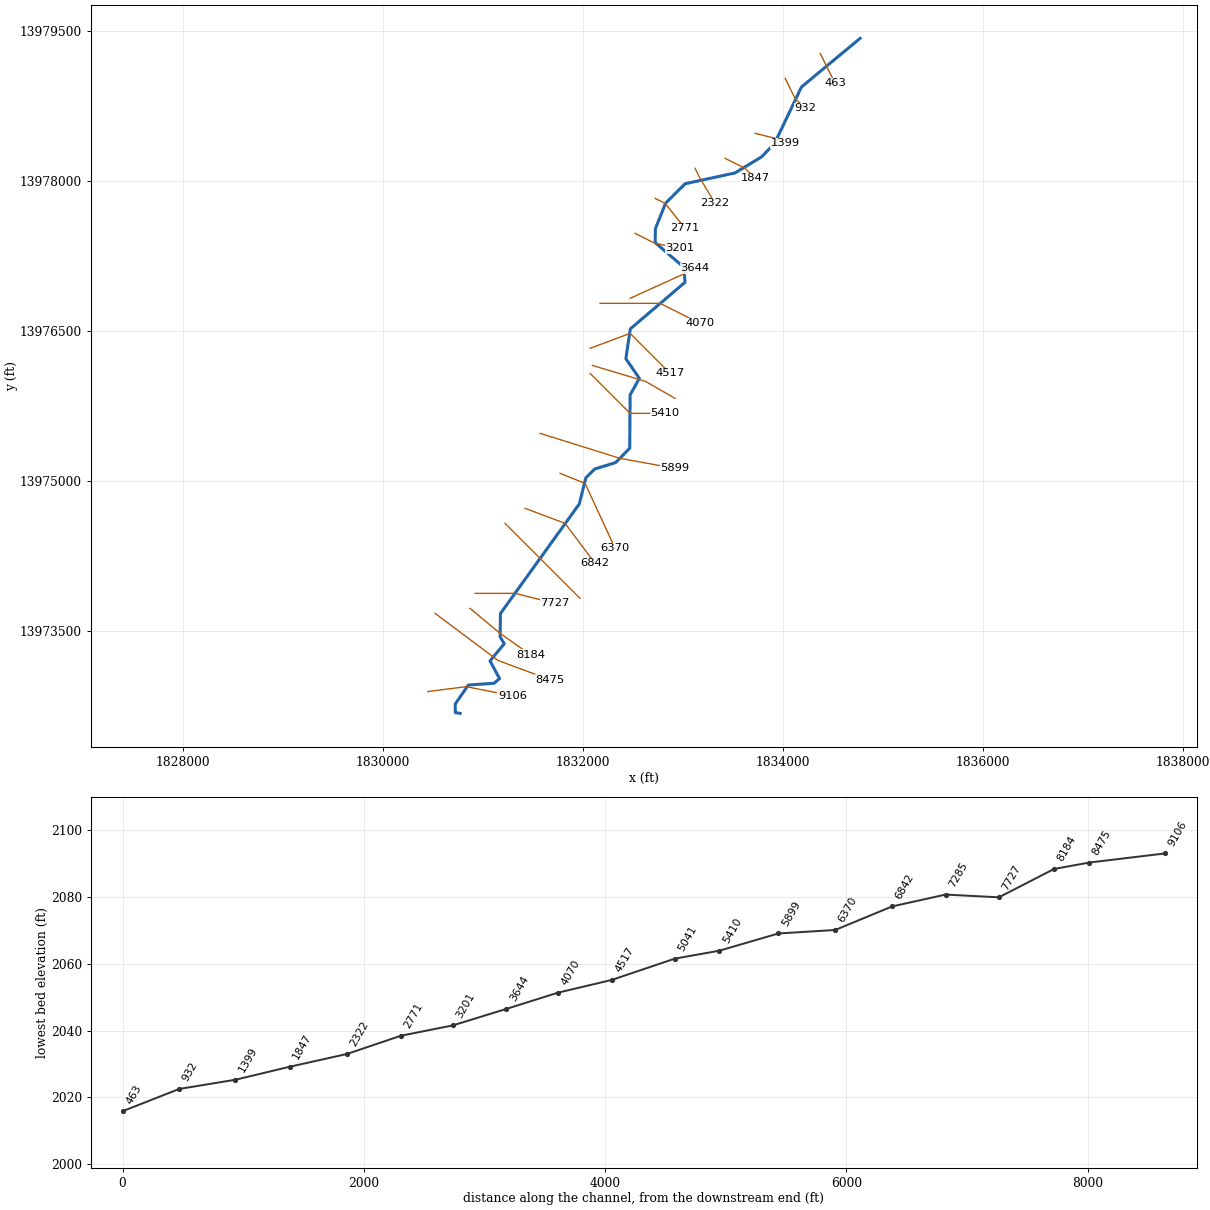
--- Stream0351.prj (project) ---

Proj Title=Stream0351 Base Level Engineering
Current Plan=p01
Default Exp/Contr=0.3,0.1
English Units
Geom File=g01
Flow File=f01
Plan File=p01
BEGIN DESCRIPTION:
Stream0351
END DESCRIPTION:

--- Stream0351.p01 (plan) ---

Plan Title=Multiple Run
Short Identifier=Multiple
Geom File=g01
Flow File=f01
Subcritical Flow
K Sum by GR= 0
Std Step Tol= 0.01
Critical Tol= 0.01
Num of Std Step Trials= 20
Max Error Tol= 0.3
Flow Tol Ratio= 0.001
Split Flow NTrial= 30
Split Flow Tol= 0.02
Split Flow Ratio= 0.02
Log Output Level= 0
Friction Slope Method= 1
Unsteady Friction Slope Method= 2
Unsteady Bridges Friction Slope Method= 1
Parabolic Critical Depth
Global Vel Dist=  1 , 1 , 1
Global Log Level= 0
CheckData=True
Encroach Param= -1, 0, 0, 0
BEGIN DESCRIPTION:
Multiple Run
END DESCRIPTION:

--- Stream0351.f01 (steady flow) ---

Flow Title=Multiple
Number of Profiles=7
Profile Names=10-year,25-year,50-year,1pct_min,100-year,1pct_plu,500-year
River Rch & RM= Stream0351,Reach-1,9106
    1116    1900    2643    1775    3542    7068    6290
River Rch & RM= Stream0351,Reach-1,7727
    1432    2469    3463    2343    4674    9326    8421
River Rch & RM= Stream0351,Reach-1,3201
    2067    3635    5165    3536    7055   14077   13027
Boundary for River Rch & Prof#=Stream0351,Reach-1,1
Up Type=0
Dn Type=3
Dn Slope=0.005
Boundary for River Rch & Prof#=Stream0351,Reach-1,2
Up Type=0
Dn Type=3
Dn Slope=0.005
Boundary for River Rch & Prof#=Stream0351,Reach-1,3
Up Type=0
Dn Type=3
Dn Slope=0.005
Boundary for River Rch & Prof#=Stream0351,Reach-1,4
Up Type=0
Dn Type=3
Dn Slope=0.005
Boundary for River Rch & Prof#=Stream0351,Reach-1,5
Up Type=0
Dn Type=3
Dn Slope=0.005
Boundary for River Rch & Prof#=Stream0351,Reach-1,6
Up Type=0
Dn Type=3
Dn Slope=0.005
Boundary for River Rch & Prof#=Stream0351,Reach-1,7
Up Type=0
Dn Type=3
Dn Slope=0.005

--- Stream0351.g01 (geometry) ---

Geom Title=Existing Conditions

River Reach=Stream0351,Reach-1
Reach XY= 30
      1830775.00     13972675.00      1830727.56     13972682.76
      1830726.92     13972769.07      1830857.86     13972958.73
      1831114.76     13972975.99      1831170.05     13973022.42
      1831074.41     13973200.00      1831217.21     13973371.58
      1831175.66     13973440.16      1831178.54     13973673.54
      1831967.12     13974768.84      1832032.85     13975031.19
      1832122.69     13975119.18      1832331.17     13975182.86
      1832471.46     13975326.46      1832475.51     13975859.79
      1832567.70     13976025.08      1832433.04     13976221.68
      1832477.06     13976519.15      1833024.03     13976985.29
      1833014.54     13977134.82      1832727.05     13977380.86
      1832727.23     13977519.07      1832830.52     13977777.43
      1833026.50     13977971.39      1833523.44     13978078.76
      1833788.21     13978238.63      1833919.17     13978372.70
      1834188.62     13978938.21      1834775.00     13979425.00

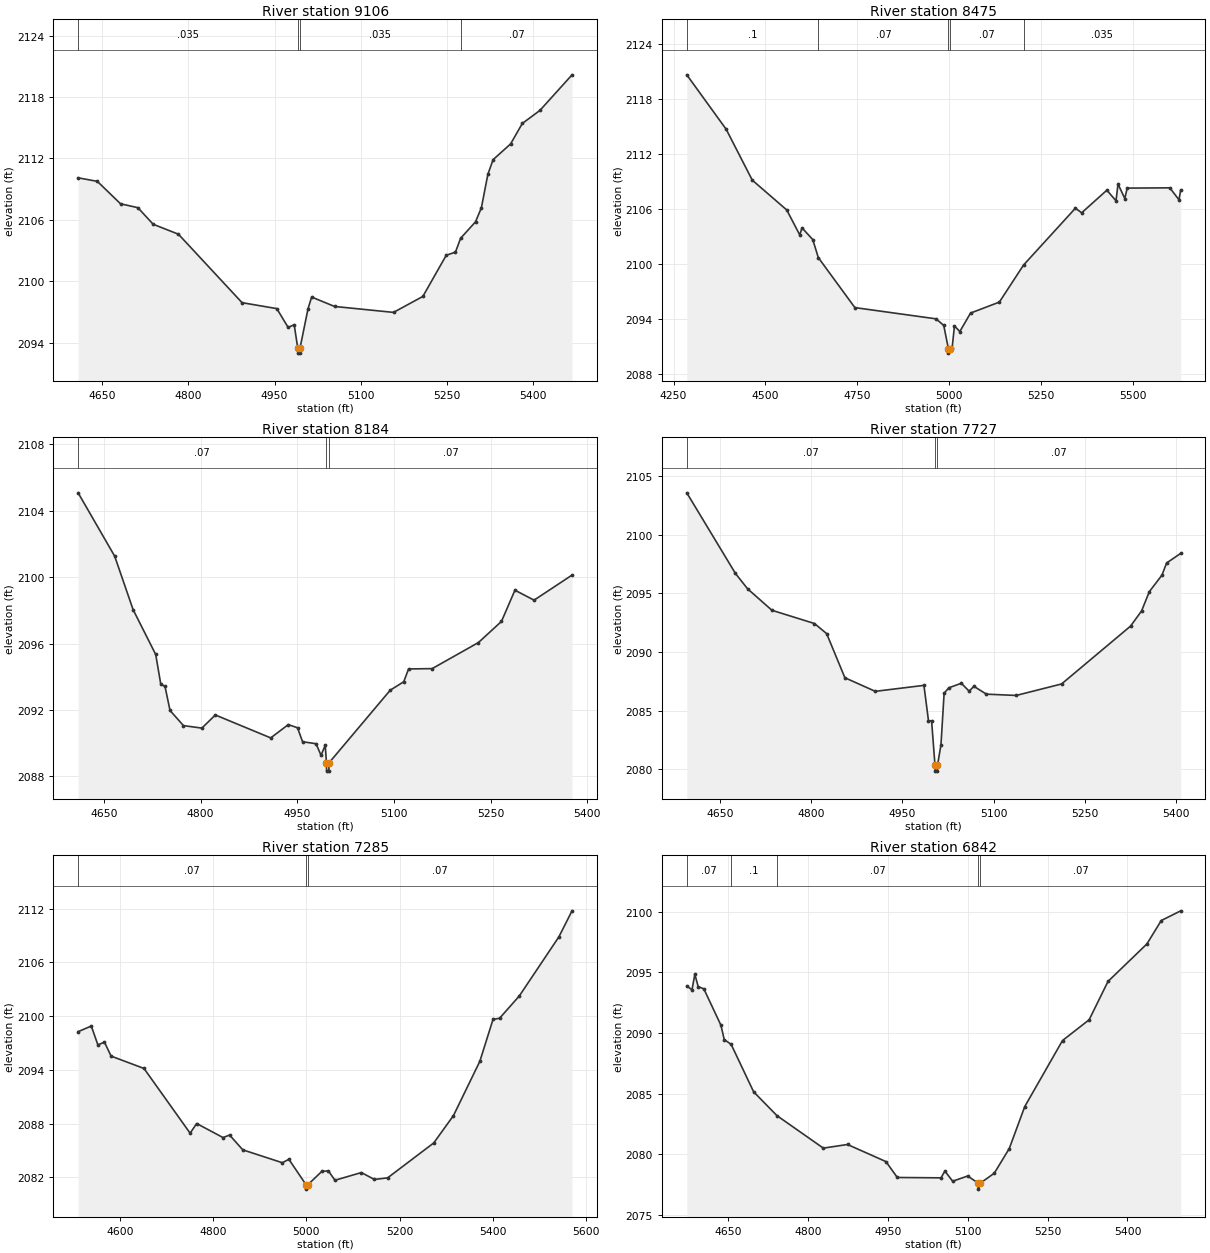
Type RM Length L Ch R = 1,9106,631,631,631
BEGIN DESCRIPTION:
Stream0351 20.0
END DESCRIPTION:
XS GIS Cut Line= 3
      1830451.73     13972893.37      1830836.42     13972942.18
      1831299.95     13972850.93
#Sta/Elev= 30
  4607.8 2110.11  4641.3 2109.76  4681.7 2107.57  4711.9 2107.19  4738.5 2105.57
  4782.5 2104.60  4893.3 2097.91  4953.8 2097.33  4973.6 2095.49  4984.1 2095.76
  4990.3 2093.48  4990.6 2092.98  4994.1 2092.98  4994.3 2093.48  5008.1 2097.29
  5014.5 2098.46  5054.4 2097.54  5157.1 2096.96  5208.2 2098.52  5248.9 2102.54
  5265.0 2102.85  5273.9 2104.20  5299.9 2105.81  5310.1 2107.18  5321.4 2110.45
  5330.5 2111.88  5361.0 2113.42  5381.4 2115.42  5412.0 2116.69  5468.0 2120.17
#Mann=4,-1,0
  4607.8   0.035       0  4990.3   0.035       0  4994.3   0.035       0
  5273.9    0.07       0
Bank Sta=4990.3,4994.3
Exp/Cntr=0.3,0.1

Type RM Length L Ch R = 1,8475,291,291,291
BEGIN DESCRIPTION:
Stream0351 19.0
END DESCRIPTION:
XS GIS Cut Line= 3
      1830525.02     13973674.98      1831153.56     13973204.83
      1831677.50     13973009.48
#Sta/Elev= 30
  4286.1 2120.68  4393.4 2114.72  4464.3 2109.16  4558.1 2105.90  4593.5 2103.17
  4599.7 2103.94  4628.9 2102.66  4644.0 2100.69  4743.5 2095.22  4964.4 2093.99
  4985.4 2093.27  4997.9 2090.74  4998.1 2090.24  5001.9 2090.74  5008.2 2090.84
  5014.5 2093.21  5029.1 2092.60  5058.2 2094.62  5136.6 2095.82  5202.6 2099.88
  5343.6 2106.09  5360.7 2105.59  5429.2 2108.06  5454.2 2106.90  5459.5 2108.74
  5478.1 2107.15  5484.5 2108.29  5600.5 2108.32  5625.5 2107.01  5630.2 2108.10
#Mann=5,-1,0
  4286.1     0.1       0  4644.0    0.07       0  4997.9    0.05       0
  5001.9    0.07       0  5202.6   0.035       0
Bank Sta=4997.9,5001.9
Exp/Cntr=0.3,0.1

Type RM Length L Ch R = 1,8184,457,457,457
BEGIN DESCRIPTION:
Stream0351 18.0
END DESCRIPTION:
XS GIS Cut Line= 3
      1830874.98     13973725.02      1831175.00     13973475.00
      1831482.65     13973259.26
#Sta/Elev= 30
  4609.9 2105.07  4666.6 2101.26  4695.2 2098.04  4730.3 2095.34  4738.2 2093.54
  4744.7 2093.42  4752.5 2091.97  4773.3 2091.06  4801.9 2090.91  4822.8 2091.70
  4908.7 2090.32  4936.0 2091.12  4950.3 2090.93  4958.1 2090.09  4979.0 2089.97
  4986.8 2089.27  4993.3 2089.88  4995.2 2088.82  4995.4 2088.32  4998.9 2088.32
  4999.2 2088.82  5094.1 2093.19  5115.1 2093.70  5122.6 2094.47  5159.2 2094.49
  5231.0 2096.06  5266.7 2097.33  5287.6 2099.21  5317.3 2098.61  5376.2 2100.12
#Mann=3,-1,0
  4609.9    0.07       0  4995.2    0.05       0  4999.2    0.07       0
Bank Sta=4995.2,4999.2
Exp/Cntr=0.3,0.1

Type RM Length L Ch R = 1,7727,442,442,442
BEGIN DESCRIPTION:
Stream0351 17.0
END DESCRIPTION:
XS GIS Cut Line= 3
      1830925.03     13973875.00      1831325.00     13973875.00
      1831725.02     13973775.00
#Sta/Elev= 30
  4595.4 2103.57  4675.4 2096.70  4695.4 2095.39  4735.4 2093.56  4805.4 2092.43
  4825.4 2091.57  4855.4 2087.81  4905.4 2086.65  4985.4 2087.16  4992.9 2084.14
  4998.0 2084.14  5003.6 2080.35  5003.9 2079.85  5007.5 2079.85  5007.7 2080.35
  5013.4 2082.08  5018.6 2086.49  5026.3 2086.95  5046.9 2087.34  5059.8 2086.66
  5067.5 2087.08  5088.1 2086.41  5137.1 2086.30  5211.8 2087.28  5325.2 2092.21
  5343.3 2093.50  5356.1 2095.15  5376.8 2096.55  5384.5 2097.59  5407.7 2098.41
#Mann=3,-1,0
  4595.4    0.07       0  5003.6    0.05       0  5007.7    0.07       0
Bank Sta=5003.6,5007.7
Exp/Cntr=0.3,0.1

Type RM Length L Ch R = 1,7285,443,443,443
BEGIN DESCRIPTION:
Stream0351 16.0
END DESCRIPTION:
XS GIS Cut Line= 3
      1831224.97     13974575.03      1831575.00     13974225.00
      1831974.99     13973825.01
#Sta/Elev= 30
  4509.8 2098.26  4538.1 2098.89  4552.3 2096.78  4566.4 2097.09  4580.6 2095.53
  4651.3 2094.15  4750.3 2086.92  4764.4 2088.00  4821.0 2086.43  4835.1 2086.71
  4863.4 2085.06  4948.3 2083.62  4962.4 2084.00  4999.2 2081.17  4999.5 2080.67
  5003.4 2081.17  5033.1 2082.65  5047.2 2082.71  5061.4 2081.66  5118.0 2082.52
  5146.2 2081.75  5174.5 2081.93  5273.5 2085.83  5315.9 2088.89  5372.5 2094.95
  5400.8 2099.63  5414.9 2099.76  5457.4 2102.26  5542.2 2108.85  5570.5 2111.76
#Mann=3,-1,0
  4509.8    0.07       0  4999.2    0.05       0  5003.4    0.07       0
Bank Sta=4999.2,5003.4
Exp/Cntr=0.3,0.1

Type RM Length L Ch R = 1,6842,472,472,472
BEGIN DESCRIPTION:
Stream0351 15.0
END DESCRIPTION:
XS GIS Cut Line= 3
      1831425.00     13974725.00      1831825.00     13974575.00
      1832125.00     13974175.00
#Sta/Elev= 30
  4572.8 2093.87  4582.6 2093.56  4587.9 2094.84  4594.2 2093.82  4604.8 2093.64
  4636.9 2090.64  4643.1 2089.46  4656.1 2089.06  4698.3 2085.15  4742.0 2083.19
  4829.1 2080.51  4874.5 2080.81  4946.6 2079.40  4968.0 2078.09  5050.0 2078.06
  5057.3 2078.62  5071.9 2077.78  5100.0 2078.21  5119.8 2077.63  5120.0 2077.13
  5124.0 2077.63  5150.0 2078.44  5178.1 2080.47  5207.3 2083.94  5278.1 2089.38
  5328.1 2091.09  5363.5 2094.25  5436.5 2097.34  5463.5 2099.27  5500.0 2100.07
#Mann=5,-1,0
  4572.8    0.07       0  4656.1     0.1       0  4742.0    0.07       0
  5119.8    0.05       0  5124.0    0.07       0
Bank Sta=5119.8,5124
Exp/Cntr=0.3,0.1

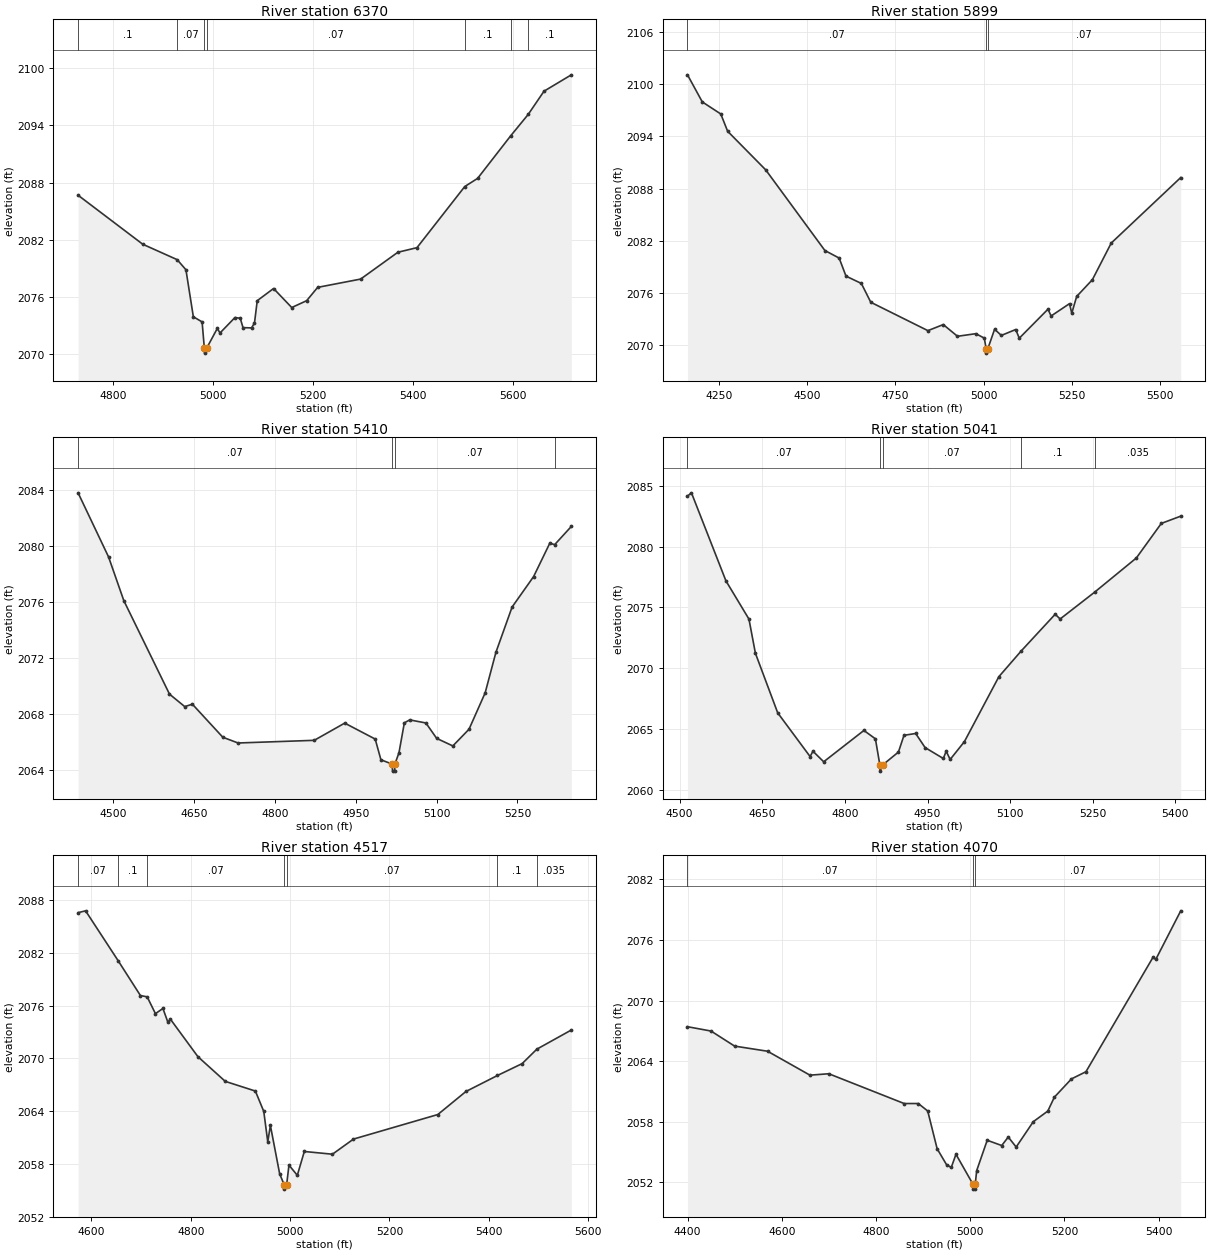
Type RM Length L Ch R = 1,6370,471,471,471
BEGIN DESCRIPTION:
Stream0351 14.0
END DESCRIPTION:
XS GIS Cut Line= 3
      1831775.00     13975075.00      1832025.00     13974975.00
      1832324.98     13974325.04
#Sta/Elev= 30
  4730.8 2086.67  4860.0 2081.52  4928.7 2079.90  4946.2 2078.84  4961.0 2073.90
  4978.5 2073.36  4983.0 2070.58  4983.3 2070.08  4987.4 2070.58  5008.8 2072.67
  5014.3 2072.20  5044.1 2073.82  5054.7 2073.74  5060.2 2072.76  5077.2 2072.73
  5083.1 2073.24  5088.6 2075.59  5121.2 2076.87  5157.5 2074.87  5187.3 2075.59
  5209.3 2076.99  5295.1 2077.86  5369.5 2080.68  5407.6 2081.16  5503.0 2087.58
  5528.7 2088.44  5594.6 2092.90  5629.9 2095.17  5661.3 2097.60  5715.9 2099.32
#Mann=7,-1,0
  4730.8     0.1       0  4928.7    0.07       0  4983.0    0.05       0
  4987.4    0.07       0  5503.0     0.1       0  5594.6    0.07       0
  5629.9     0.1       0
Bank Sta=4983,4987.4
Exp/Cntr=0.3,0.1

Type RM Length L Ch R = 1,5899,489,489,489
BEGIN DESCRIPTION:
Stream0351 13.0
END DESCRIPTION:
XS GIS Cut Line= 3
      1831574.97     13975475.01      1832375.00     13975225.00
      1832925.00     13975125.00
#Sta/Elev= 30
  4161.5 2101.10  4203.4 2097.98  4255.8 2096.59  4275.2 2094.60  4383.1 2090.15
  4550.7 2080.86  4591.1 2079.99  4610.5 2077.91  4653.9 2077.07  4680.7 2074.90
  4842.5 2071.63  4886.0 2072.33  4926.3 2070.98  4978.2 2071.28  5002.2 2070.77
  5007.5 2069.54  5007.8 2069.04  5012.2 2069.54  5031.4 2071.79  5050.5 2071.08
  5091.2 2071.76  5101.3 2070.76  5182.6 2074.10  5191.5 2073.32  5243.6 2074.74
  5250.0 2073.64  5263.9 2075.57  5308.4 2077.50  5361.8 2081.72  5558.7 2089.27
#Mann=3,-1,0
  4161.5    0.07       0  5007.5    0.05       0  5012.2    0.07       0
Bank Sta=5007.5,5012.2
Exp/Cntr=0.3,0.1

Type RM Length L Ch R = 1,5410,369,369,369
BEGIN DESCRIPTION:
Stream0351 12.0
END DESCRIPTION:
XS GIS Cut Line= 3
      1832074.98     13976075.02      1832475.00     13975675.00
      1832824.99     13975675.00
#Sta/Elev= 30
  4434.3 2083.77  4490.9 2079.19  4519.2 2076.07  4604.0 2069.39  4632.3 2068.50
  4646.5 2068.67  4703.0 2066.31  4731.3 2065.90  4872.7 2066.09  4929.3 2067.32
  4985.9 2066.18  4996.5 2064.70  5017.6 2064.39  5018.0 2063.89  5022.1 2063.89
  5022.4 2064.39  5030.0 2065.20  5040.0 2067.34  5050.0 2067.55  5080.0 2067.33
  5100.0 2066.23  5130.0 2065.69  5160.0 2066.88  5190.0 2069.48  5210.0 2072.38
  5240.0 2075.61  5280.0 2077.79  5310.0 2080.17  5319.1 2080.07  5350.0 2081.37
#Mann=4,-1,0
  4434.3    0.07       0  5017.6    0.05       0  5022.4    0.07       0
  5319.1   0.035       0
Bank Sta=5017.6,5022.4
Exp/Cntr=0.3,0.1

Type RM Length L Ch R = 1,5041,524,524,524
BEGIN DESCRIPTION:
Stream0351 11.0
END DESCRIPTION:
XS GIS Cut Line= 3
      1832098.14     13976154.31      1832627.01     13975995.77
      1832925.02     13975824.99
#Sta/Elev= 30
  4514.2 2084.17  4521.4 2084.44  4584.0 2077.19  4625.8 2074.04  4637.5 2071.23
  4678.0 2066.32  4736.8 2062.72  4742.0 2063.16  4761.5 2062.29  4834.5 2064.87
  4855.4 2064.18  4863.5 2062.02  4863.8 2061.52  4868.3 2062.02  4897.2 2063.09
  4907.3 2064.47  4928.5 2064.62  4945.6 2063.46  4978.7 2062.56  4983.9 2063.16
  4991.1 2062.48  5017.0 2063.95  5079.6 2069.30  5120.0 2071.41  5181.8 2074.44
  5190.8 2074.05  5253.2 2076.25  5329.1 2079.07  5374.5 2081.92  5409.8 2082.52
#Mann=5,-1,0
  4514.2    0.07       0  4863.5    0.05       0  4868.3    0.07       0
  5120.0     0.1       0  5253.2   0.035       0
Bank Sta=4863.5,4868.3
Exp/Cntr=0.3,0.1

Type RM Length L Ch R = 1,4517,447,447,447
BEGIN DESCRIPTION:
Stream0351 10.0
END DESCRIPTION:
XS GIS Cut Line= 3
      1832075.03     13976325.01      1832475.00     13976475.00
      1832875.04     13976074.96
#Sta/Elev= 30
  4573.3 2086.57  4588.4 2086.78  4653.7 2081.13  4698.8 2077.15  4712.4 2077.00
  4729.0 2075.09  4744.1 2075.68  4753.9 2074.14  4759.3 2074.45  4814.5 2070.20
  4869.6 2067.39  4930.2 2066.29  4947.1 2063.97  4955.1 2060.52  4960.4 2062.38
  4979.1 2056.87  4988.2 2055.64  4988.6 2055.14  4993.1 2055.64  4997.8 2057.87
  5014.6 2056.71  5028.7 2059.42  5085.3 2059.11  5127.7 2060.83  5297.4 2063.62
  5354.0 2066.24  5417.5 2068.06  5467.2 2069.41  5496.7 2071.05  5566.2 2073.23
#Mann=7,-1,0
  4573.3    0.07       0  4653.7     0.1       0  4712.4    0.07       0
  4988.2    0.05       0  4993.1    0.07       0  5417.5     0.1       0
  5496.7   0.035       0
Bank Sta=4988.2,4993.1
Exp/Cntr=0.3,0.1

Type RM Length L Ch R = 1,4070,426,426,426
BEGIN DESCRIPTION:
Stream0351 9.0
END DESCRIPTION:
XS GIS Cut Line= 3
      1832175.02     13976775.00      1832775.00     13976775.00
      1833175.01     13976575.00
#Sta/Elev= 30
  4399.8 2067.41  4449.8 2066.98  4499.8 2065.49  4569.8 2064.98  4659.8 2062.61
  4699.8 2062.75  4859.8 2059.80  4889.8 2059.80  4909.8 2059.06  4929.8 2055.32
  4949.8 2053.74  4959.8 2053.47  4969.8 2054.77  5005.7 2051.82  5006.0 2051.32
  5010.3 2051.32  5010.7 2051.82  5013.8 2053.16  5036.1 2056.16  5066.9 2055.64
  5080.8 2056.48  5097.6 2055.49  5133.9 2058.00  5164.7 2059.05  5178.7 2060.43
  5215.0 2062.24  5245.7 2062.95  5388.3 2074.30  5393.9 2074.07  5447.0 2078.89
#Mann=3,-1,0
  4399.8    0.07       0  5005.7    0.05       0  5010.7    0.07       0
Bank Sta=5005.7,5010.7
Exp/Cntr=0.3,0.1

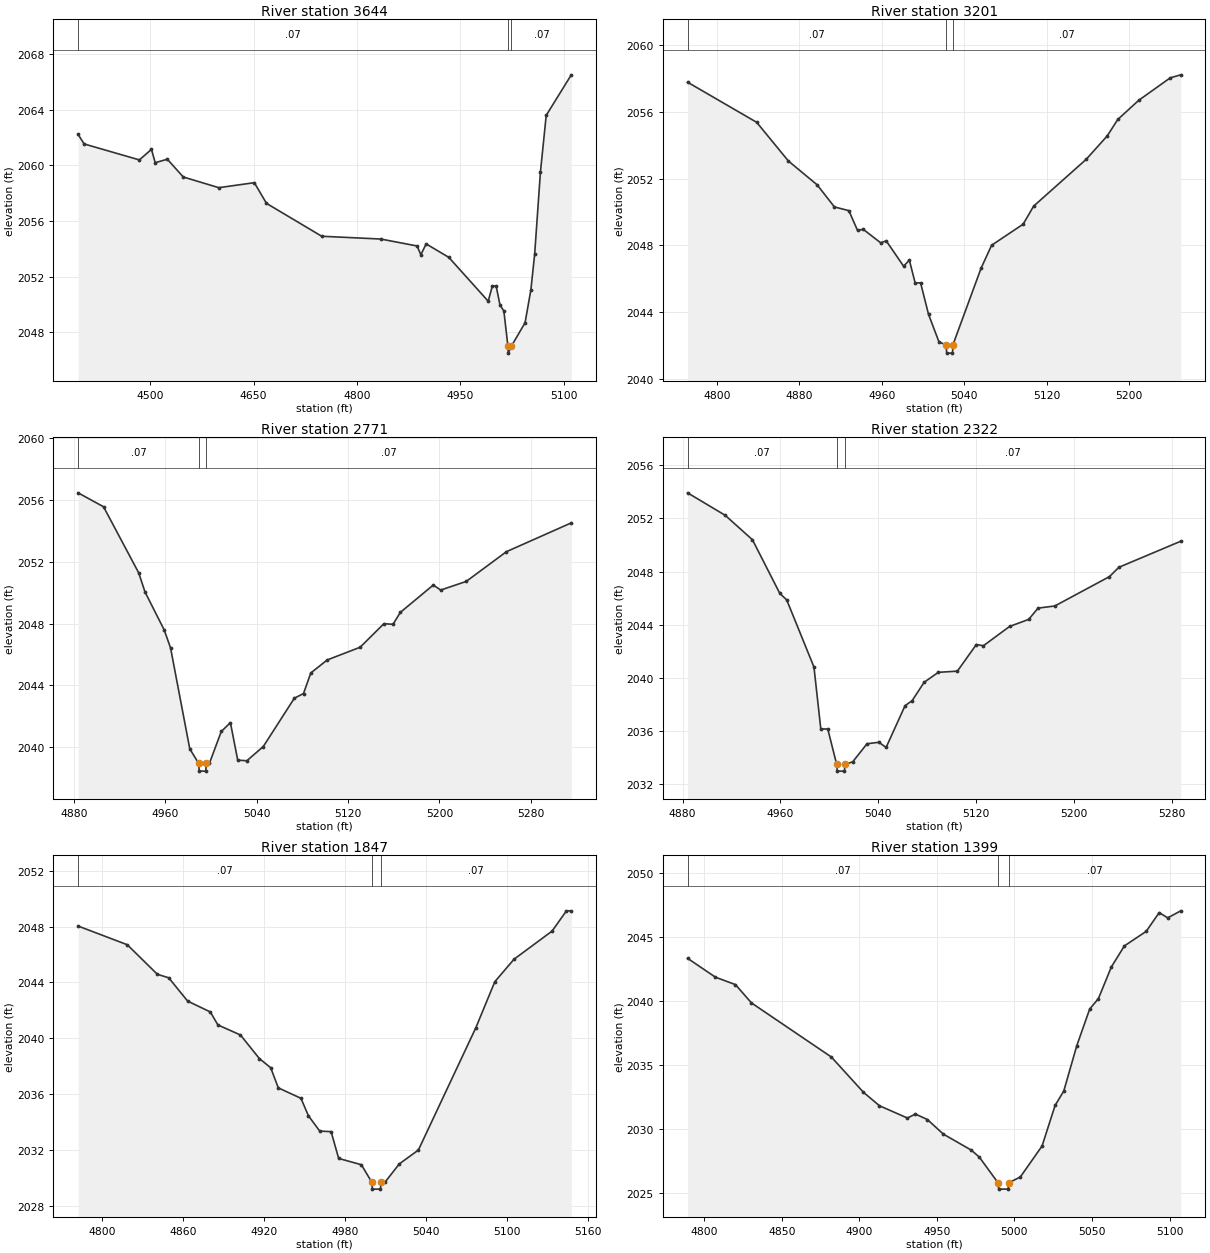
Type RM Length L Ch R = 1,3644,443,443,443
BEGIN DESCRIPTION:
Stream0351 8.0
END DESCRIPTION:
XS GIS Cut Line= 3
      1832475.00     13976825.00      1833025.00     13977075.00
      1833125.04     13977125.02
#Sta/Elev= 30
  4395.3 2062.24  4404.1 2061.55  4484.3 2060.40  4501.8 2061.16  4507.3 2060.20
  4524.9 2060.45  4548.0 2059.17  4599.6 2058.40  4651.2 2058.76  4668.8 2057.27
  4749.0 2054.90  4834.7 2054.70  4887.4 2054.20  4892.9 2053.57  4900.6 2054.35
  4933.5 2053.38  4990.7 2050.22  4996.7 2051.32  5002.2 2051.32  5007.8 2049.94
  5013.4 2049.52  5019.3 2046.98  5019.7 2046.48  5024.3 2046.98  5044.2 2048.67
  5052.6 2051.03  5058.1 2053.59  5066.5 2059.53  5074.9 2063.61  5111.3 2066.53
#Mann=3,-1,0
  4395.3    0.07       0  5019.3    0.05       0  5024.3    0.07       0
Bank Sta=5019.3,5024.3
Exp/Cntr=0.3,0.1

Type RM Length L Ch R = 1,3201,430,430,430
BEGIN DESCRIPTION:
Stream0351 7.0
END DESCRIPTION:
XS GIS Cut Line= 3
      1832525.01     13977474.99      1832725.00     13977375.00
      1832974.96     13977325.01
#Sta/Elev= 30
  4771.6 2057.76  4838.7 2055.36  4869.4 2053.05  4897.4 2051.62  4914.1 2050.30
  4928.1 2050.08  4936.5 2048.90  4942.1 2048.96  4958.9 2048.16  4964.4 2048.27
  4981.2 2046.76  4986.8 2047.12  4992.4 2045.76  4997.7 2045.76  5005.4 2043.88
  5015.6 2042.22  5022.5 2042.06  5023.0 2041.56  5028.6 2041.56  5029.1 2042.06
  5056.4 2046.64  5066.6 2048.01  5097.2 2049.27  5107.4 2050.35  5158.4 2053.15
  5178.8 2054.55  5189.0 2055.53  5209.4 2056.68  5239.9 2058.02  5250.1 2058.20
#Mann=3,-1,0
  4771.6    0.07       0  5022.5    0.05       0  5029.1    0.07       0
Bank Sta=5022.5,5029.1
Exp/Cntr=0.3,0.1

Type RM Length L Ch R = 1,2771,449,449,449
BEGIN DESCRIPTION:
Stream0351 6.0
END DESCRIPTION:
XS GIS Cut Line= 3
      1832725.04     13977824.98      1832825.00     13977775.00
      1833024.99     13977525.01
#Sta/Elev= 30
  4883.6 2056.44  4905.9 2055.54  4936.7 2051.27  4942.2 2050.04  4959.0 2047.59
  4964.6 2046.42  4981.4 2039.91  4989.2 2038.97  4989.7 2038.47  4995.4 2038.47
  4995.9 2038.97  4998.6 2038.97  5009.0 2041.03  5017.0 2041.60  5023.4 2039.18
  5031.4 2039.14  5045.8 2040.06  5073.0 2043.18  5081.0 2043.48  5087.4 2044.81
  5101.8 2045.65  5130.6 2046.47  5151.4 2047.99  5159.4 2047.95  5165.8 2048.72
  5194.7 2050.49  5201.1 2050.16  5223.5 2050.72  5258.7 2052.64  5315.5 2054.50
#Mann=3,-1,0
  4883.6    0.07       0  4989.2    0.05       0  4995.9    0.07       0
Bank Sta=4989.2,4995.9
Exp/Cntr=0.3,0.1

Type RM Length L Ch R = 1,2322,475,475,475
BEGIN DESCRIPTION:
Stream0351 5.0
END DESCRIPTION:
XS GIS Cut Line= 3
      1833124.99     13978125.02      1833175.00     13978025.00
      1833325.02     13977774.97
#Sta/Elev= 30
  4884.0 2053.93  4914.8 2052.24  4937.1 2050.40  4959.5 2046.36  4965.1 2045.88
  4987.4 2040.83  4993.0 2036.17  4998.7 2036.17  5006.0 2033.50  5006.5 2033.00
  5012.3 2033.00  5012.8 2033.50  5019.1 2033.70  5030.8 2035.06  5040.5 2035.17
  5046.4 2034.78  5061.9 2037.92  5067.7 2038.30  5077.5 2039.68  5089.1 2040.43
  5104.7 2040.52  5120.2 2042.52  5126.0 2042.43  5147.4 2043.88  5163.0 2044.41
  5170.7 2045.26  5184.4 2045.42  5229.1 2047.63  5236.8 2048.33  5287.4 2050.29
#Mann=3,-1,0
  4884.0    0.07       0  5006.0    0.05       0  5012.8    0.07       0
Bank Sta=5006,5012.8
Exp/Cntr=0.3,0.1

Type RM Length L Ch R = 1,1847,448,448,448
BEGIN DESCRIPTION:
Stream0351 4.0
END DESCRIPTION:
XS GIS Cut Line= 3
      1833424.96     13978225.02      1833625.00     13978125.00
      1833725.02     13978024.98
#Sta/Elev= 30
  4782.4 2048.04  4818.8 2046.70  4841.1 2044.58  4849.5 2044.33  4863.5 2042.66
  4880.3 2041.88  4885.9 2040.95  4902.6 2040.23  4916.6 2038.54  4925.0 2037.88
  4930.6 2036.44  4947.4 2035.69  4952.9 2034.44  4961.3 2033.34  4969.7 2033.30
  4975.3 2031.38  4992.1 2030.93  4999.8 2029.68  5000.3 2029.18  5006.2 2029.18
  5006.7 2029.68  5009.6 2029.68  5020.2 2030.99  5034.3 2031.98  5076.8 2040.74
  5090.9 2044.05  5105.1 2045.66  5133.3 2047.68  5143.9 2049.13  5147.5 2049.13
#Mann=3,-1,0
  4782.4    0.07       0  4999.8    0.05       0  5006.7    0.07       0
Bank Sta=4999.8,5006.7
Exp/Cntr=0.3,0.1

Type RM Length L Ch R = 1,1399,467,467,467
BEGIN DESCRIPTION:
Stream0351 3.0
END DESCRIPTION:
XS GIS Cut Line= 3
      1833725.02     13978474.99      1833925.00     13978425.00
      1834024.97     13978375.02
#Sta/Elev= 30
  4789.3 2043.36  4807.3 2041.88  4820.2 2041.30  4830.5 2039.87  4882.0 2035.64
  4902.7 2032.88  4913.0 2031.83  4931.0 2030.87  4936.2 2031.18  4943.9 2030.75
  4954.2 2029.61  4972.2 2028.36  4977.4 2027.81  4989.4 2025.81  4989.9 2025.31
  4995.9 2025.31  4996.4 2025.81  5003.8 2026.26  5017.8 2028.68  5026.2 2031.85
  5031.8 2032.98  5040.2 2036.53  5048.5 2039.39  5054.1 2040.20  5062.5 2042.69
  5070.9 2044.33  5084.9 2045.46  5093.3 2046.93  5098.8 2046.52  5107.2 2047.07
#Mann=3,-1,0
  4789.3    0.07       0  4989.4    0.05       0  4996.4    0.07       0
Bank Sta=4989.4,4996.4
Exp/Cntr=0.3,0.1

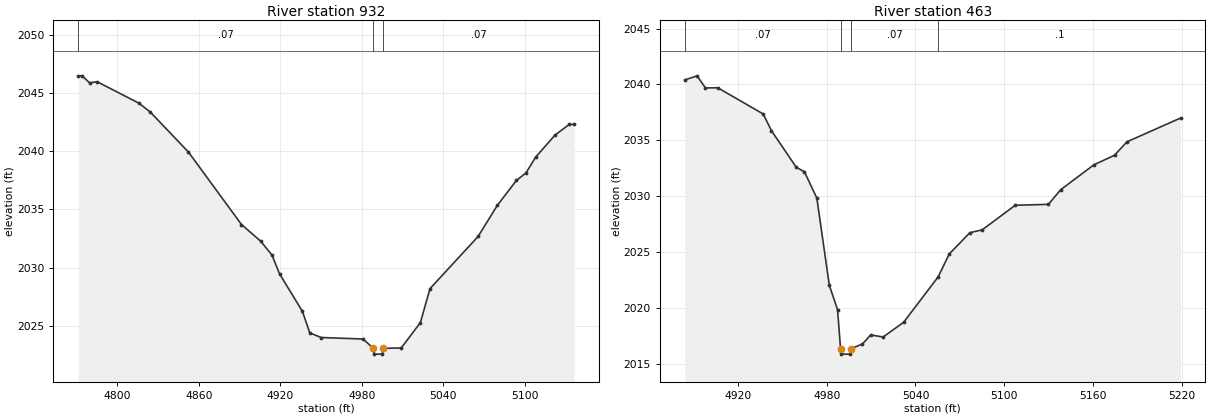
Type RM Length L Ch R = 1,932,469,469,469
BEGIN DESCRIPTION:
Stream0351 2.0
END DESCRIPTION:
XS GIS Cut Line= 3
      1834024.98     13979025.04      1834125.00     13978825.00
      1834225.02     13978724.98
#Sta/Elev= 30
  4771.3 2046.49  4774.1 2046.49  4779.7 2045.89  4785.3 2045.98  4816.1 2044.13
  4824.4 2043.37  4852.4 2039.94  4891.5 2033.70  4905.5 2032.28  4913.9 2031.08
  4919.5 2029.46  4936.3 2026.24  4941.8 2024.37  4950.2 2023.98  4981.0 2023.85
  4988.6 2023.05  4989.1 2022.55  4995.2 2022.55  4995.7 2023.05  5009.1 2023.08
  5023.2 2025.26  5030.3 2028.19  5065.7 2032.67  5079.8 2035.34  5093.9 2037.49
  5101.0 2038.15  5108.1 2039.50  5122.2 2041.38  5132.8 2042.31  5136.4 2042.31
#Mann=3,-1,0
  4771.3    0.07       0  4988.6    0.05       0  4995.7    0.07       0
Bank Sta=4988.6,4995.7
Exp/Cntr=0.3,0.1

Type RM Length L Ch R = 1,463,0,0,0
BEGIN DESCRIPTION:
Stream0351 1.0
END DESCRIPTION:
XS GIS Cut Line= 3
      1834375.00     13979274.99      1834425.00     13979175.00
      1834525.00     13978975.00
#Sta/Elev= 30
  4883.9 2040.40  4892.3 2040.77  4897.9 2039.69  4906.3 2039.70  4937.0 2037.36
  4942.6 2035.86  4959.4 2032.59  4964.9 2032.19  4973.3 2029.83  4981.7 2022.05
  4987.3 2019.86  4989.3 2016.39  4989.8 2015.89  4996.0 2015.89  4996.5 2016.39
  5004.1 2016.79  5009.7 2017.61  5018.1 2017.42  5032.0 2018.74  5055.4 2022.81
  5062.8 2024.84  5076.8 2026.75  5085.1 2027.00  5107.5 2029.20  5129.9 2029.28
  5138.2 2030.59  5160.6 2032.81  5174.6 2033.67  5183.0 2034.87  5219.3 2037.00
#Mann=4,-1,0
  4883.9    0.07       0  4989.3    0.05       0  4996.5    0.07       0
  5055.4     0.1       0
Bank Sta=4989.3,4996.5
Exp/Cntr=0.3,0.1

Chan Stop Cuts=-1