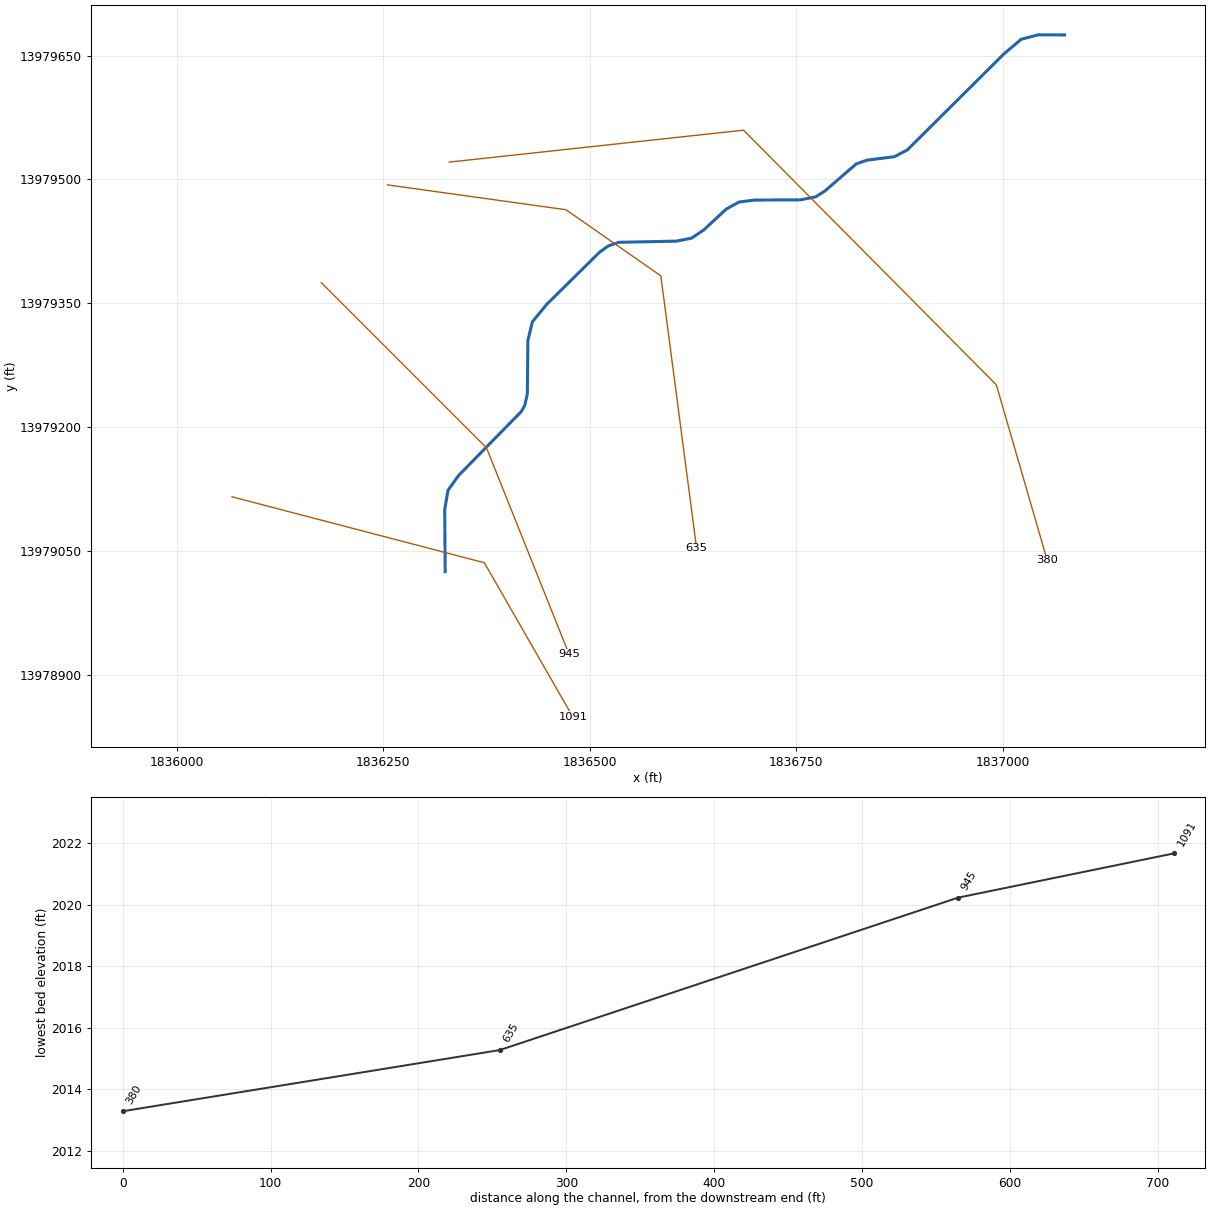
--- Stream0352.prj (project) ---

Proj Title=Stream0352 Base Level Engineering
Current Plan=p01
Default Exp/Contr=0.3,0.1
English Units
Geom File=g01
Flow File=f01
Plan File=p01
BEGIN DESCRIPTION:
Stream0352
END DESCRIPTION:

--- Stream0352.p01 (plan) ---

Plan Title=Multiple Run
Short Identifier=Multiple
Geom File=g01
Flow File=f01
Subcritical Flow
K Sum by GR= 0
Std Step Tol= 0.01
Critical Tol= 0.01
Num of Std Step Trials= 20
Max Error Tol= 0.3
Flow Tol Ratio= 0.001
Split Flow NTrial= 30
Split Flow Tol= 0.02
Split Flow Ratio= 0.02
Log Output Level= 0
Friction Slope Method= 1
Unsteady Friction Slope Method= 2
Unsteady Bridges Friction Slope Method= 1
Parabolic Critical Depth
Global Vel Dist=  1 , 1 , 1
Global Log Level= 0
CheckData=True
Encroach Param= -1, 0, 0, 0
BEGIN DESCRIPTION:
Multiple Run
END DESCRIPTION:

--- Stream0352.f01 (steady flow) ---

Flow Title=Multiple
Number of Profiles=7
Profile Names=10-year,25-year,50-year,1pct_min,100-year,1pct_plu,500-year
River Rch & RM= Stream0352,Reach-1,1091
     681    1127    1538    1016    2028    4046    3479
Boundary for River Rch & Prof#=Stream0352,Reach-1,1
Up Type=0
Dn Type=3
Dn Slope=0.005
Boundary for River Rch & Prof#=Stream0352,Reach-1,2
Up Type=0
Dn Type=3
Dn Slope=0.005
Boundary for River Rch & Prof#=Stream0352,Reach-1,3
Up Type=0
Dn Type=3
Dn Slope=0.005
Boundary for River Rch & Prof#=Stream0352,Reach-1,4
Up Type=0
Dn Type=3
Dn Slope=0.005
Boundary for River Rch & Prof#=Stream0352,Reach-1,5
Up Type=0
Dn Type=3
Dn Slope=0.005
Boundary for River Rch & Prof#=Stream0352,Reach-1,6
Up Type=0
Dn Type=3
Dn Slope=0.005
Boundary for River Rch & Prof#=Stream0352,Reach-1,7
Up Type=0
Dn Type=3
Dn Slope=0.005

--- Stream0352.g01 (geometry) ---

Geom Title=Existing Conditions

River Reach=Stream0352,Reach-1
Reach XY= 30
      1836325.00     13979025.00      1836324.41     13979100.24
      1836328.39     13979123.59      1836341.47     13979141.75
      1836417.12     13979218.84      1836421.37     13979226.50
      1836424.47     13979240.22      1836425.13     13979304.95
      1836430.52     13979327.44      1836447.85     13979348.58
      1836511.67     13979411.61      1836522.56     13979419.48
      1836535.47     13979423.84      1836604.90     13979425.25
      1836623.40     13979428.86      1836638.13     13979438.82
      1836665.37     13979464.11      1836680.97     13979472.65
      1836700.00     13979475.00      1836754.91     13979475.23
      1836773.42     13979478.82      1836784.65     13979485.84
      1836822.83     13979518.86      1836835.71     13979523.28
      1836868.97     13979527.50      1836884.68     13979535.76
      1837001.55     13979651.96      1837022.48     13979669.69
      1837043.12     13979675.07      1837075.00     13979675.00

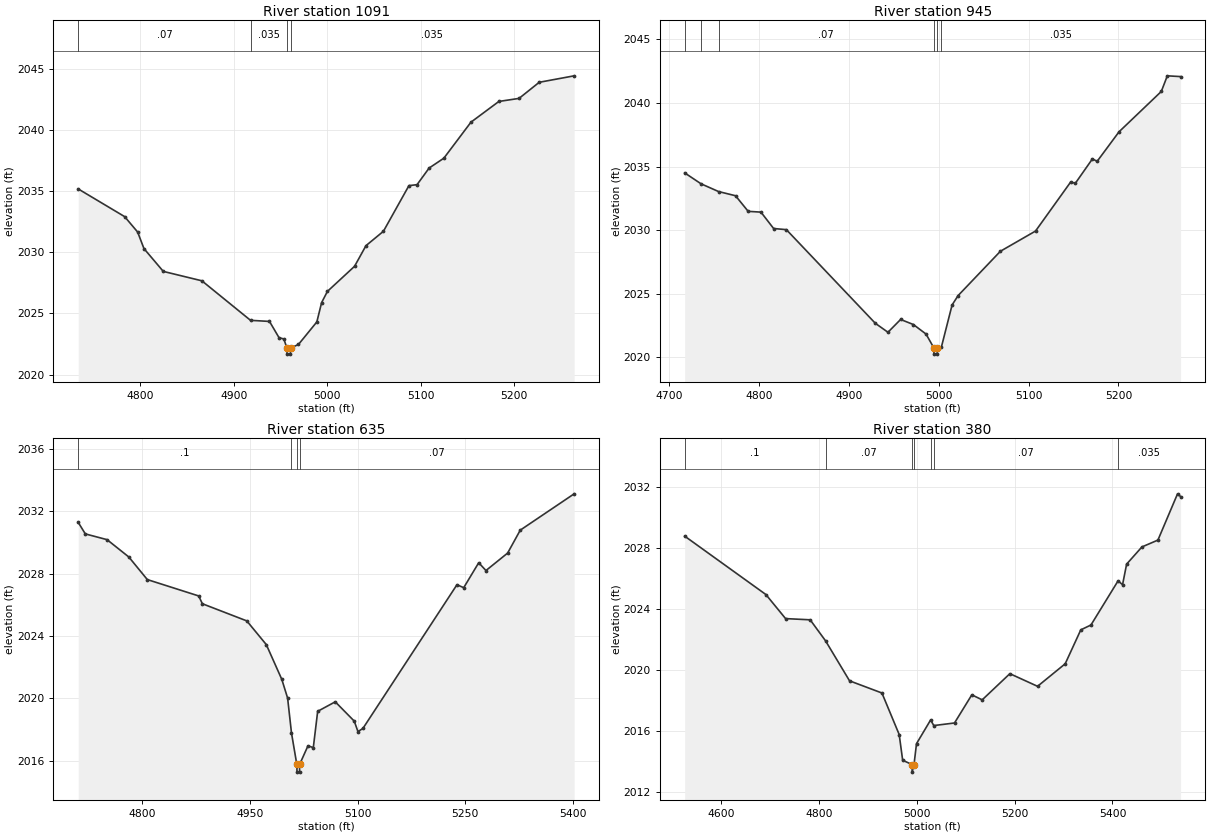
Type RM Length L Ch R = 1,1091,146,146,146
BEGIN DESCRIPTION:
Stream0352 0.2
END DESCRIPTION:
XS GIS Cut Line= 3
      1836066.89     13979115.66      1836372.41     13979035.81
      1836479.56     13978849.17
#Sta/Elev= 30
  4733.5 2035.21  4783.2 2032.94  4797.1 2031.68  4803.9 2030.32  4824.6 2028.45
  4865.9 2027.68  4918.0 2024.44  4938.3 2024.35  4948.5 2023.02  4953.7 2022.91
  4956.9 2022.17  4957.2 2021.67  4960.7 2021.67  4960.9 2022.17  4969.3 2022.46
  4989.0 2024.31  4994.1 2025.89  5000.3 2026.81  5029.4 2028.87  5041.6 2030.56
  5060.3 2031.74  5087.6 2035.48  5096.3 2035.56  5109.2 2036.92  5125.0 2037.73
  5154.0 2040.68  5183.9 2042.38  5205.5 2042.63  5227.1 2043.95  5264.5 2044.48
#Mann=4,-1,0
  4733.5    0.07       0  4918.0   0.035       0  4956.9   0.035       0
  4960.9   0.035       0
Bank Sta=4956.9,4960.9
Exp/Cntr=0.3,0.1

Type RM Length L Ch R = 1,945,310,310,310
BEGIN DESCRIPTION:
Stream0352 1.0
END DESCRIPTION:
XS GIS Cut Line= 3
      1836174.98     13979375.02      1836375.00     13979175.00
      1836474.99     13978925.03
#Sta/Elev= 30
  4717.1 2034.50  4735.3 2033.64  4754.8 2033.03  4773.7 2032.70  4787.8 2031.47
  4802.0 2031.41  4816.1 2030.12  4830.3 2030.03  4929.3 2022.66  4943.4 2021.95
  4957.5 2022.96  4971.7 2022.56  4985.8 2021.81  4994.4 2020.73  4994.7 2020.23
  4998.2 2020.23  4998.4 2020.73  5002.9 2020.79  5014.8 2024.10  5021.5 2024.84
  5068.6 2028.33  5107.7 2029.92  5146.7 2033.77  5152.1 2033.69  5171.0 2035.60
  5176.3 2035.41  5200.6 2037.73  5247.7 2040.91  5254.4 2042.14  5269.2 2042.08
#Mann=6,-1,0
  4717.1    0.07       0  4735.3     0.1       0  4754.8    0.07       0
  4994.4    0.05       0  4998.4    0.07       0  5002.9   0.035       0
Bank Sta=4994.4,4998.4
Exp/Cntr=0.3,0.1

Type RM Length L Ch R = 1,635,255,255,255
BEGIN DESCRIPTION:
Stream0352 0.0
END DESCRIPTION:
XS GIS Cut Line= 4
      1836255.18     13979493.37      1836471.27     13979463.27
      1836586.14     13979383.23      1836629.46     13979053.14
#Sta/Elev= 30
  4710.5 2031.29  4720.4 2030.55  4750.7 2030.18  4781.0 2029.07  4806.8 2027.62
  4878.4 2026.57  4883.5 2026.07  4945.4 2024.97  4972.6 2023.45  4994.2 2021.22
  5002.3 2020.02  5007.7 2017.78  5015.1 2015.77  5015.4 2015.27  5018.9 2015.27
  5019.1 2015.77  5030.7 2016.96  5038.1 2016.84  5044.2 2019.17  5068.7 2019.78
  5095.2 2018.54  5100.3 2017.87  5107.2 2018.07  5238.3 2027.29  5247.7 2027.10
  5268.6 2028.70  5278.7 2028.20  5308.9 2029.32  5326.5 2030.79  5401.6 2033.12
#Mann=4,-1,0
  4710.5     0.1       0  5007.7    0.07       0  5015.1    0.05       0
  5019.1    0.07       0
Bank Sta=5015.1,5019.1
Exp/Cntr=0.3,0.1

Type RM Length L Ch R = 1,380,0,0,0
BEGIN DESCRIPTION:
Stream0352 0.1
END DESCRIPTION:
XS GIS Cut Line= 4
      1836329.90     13979520.95      1836686.26     13979559.63
      1836992.41     13979251.23      1837053.94     13979038.98
#Sta/Elev= 30
  4525.3 2028.79  4691.4 2024.95  4731.6 2023.37  4781.9 2023.29  4813.3 2021.91
  4862.4 2019.28  4928.6 2018.48  4963.9 2015.75  4971.0 2014.06  4990.2 2013.78
  4990.4 2013.28  4994.2 2013.78  4999.3 2015.15  5028.2 2016.71  5034.6 2016.34
  5077.0 2016.51  5112.4 2018.36  5133.6 2018.03  5190.2 2019.75  5246.8 2018.92
  5303.3 2020.40  5335.2 2022.63  5356.0 2022.95  5411.4 2025.85  5420.6 2025.60
  5428.9 2026.95  5460.2 2028.08  5492.9 2028.53  5533.0 2031.57  5539.3 2031.39
#Mann=7,-1,0
  4525.3     0.1       0  4813.3    0.07       0  4990.2    0.05       0
  4994.2    0.07       0  5028.2     0.1       0  5034.6    0.07       0
  5411.4   0.035       0
Bank Sta=4990.2,4994.2
Exp/Cntr=0.3,0.1

Chan Stop Cuts=-1