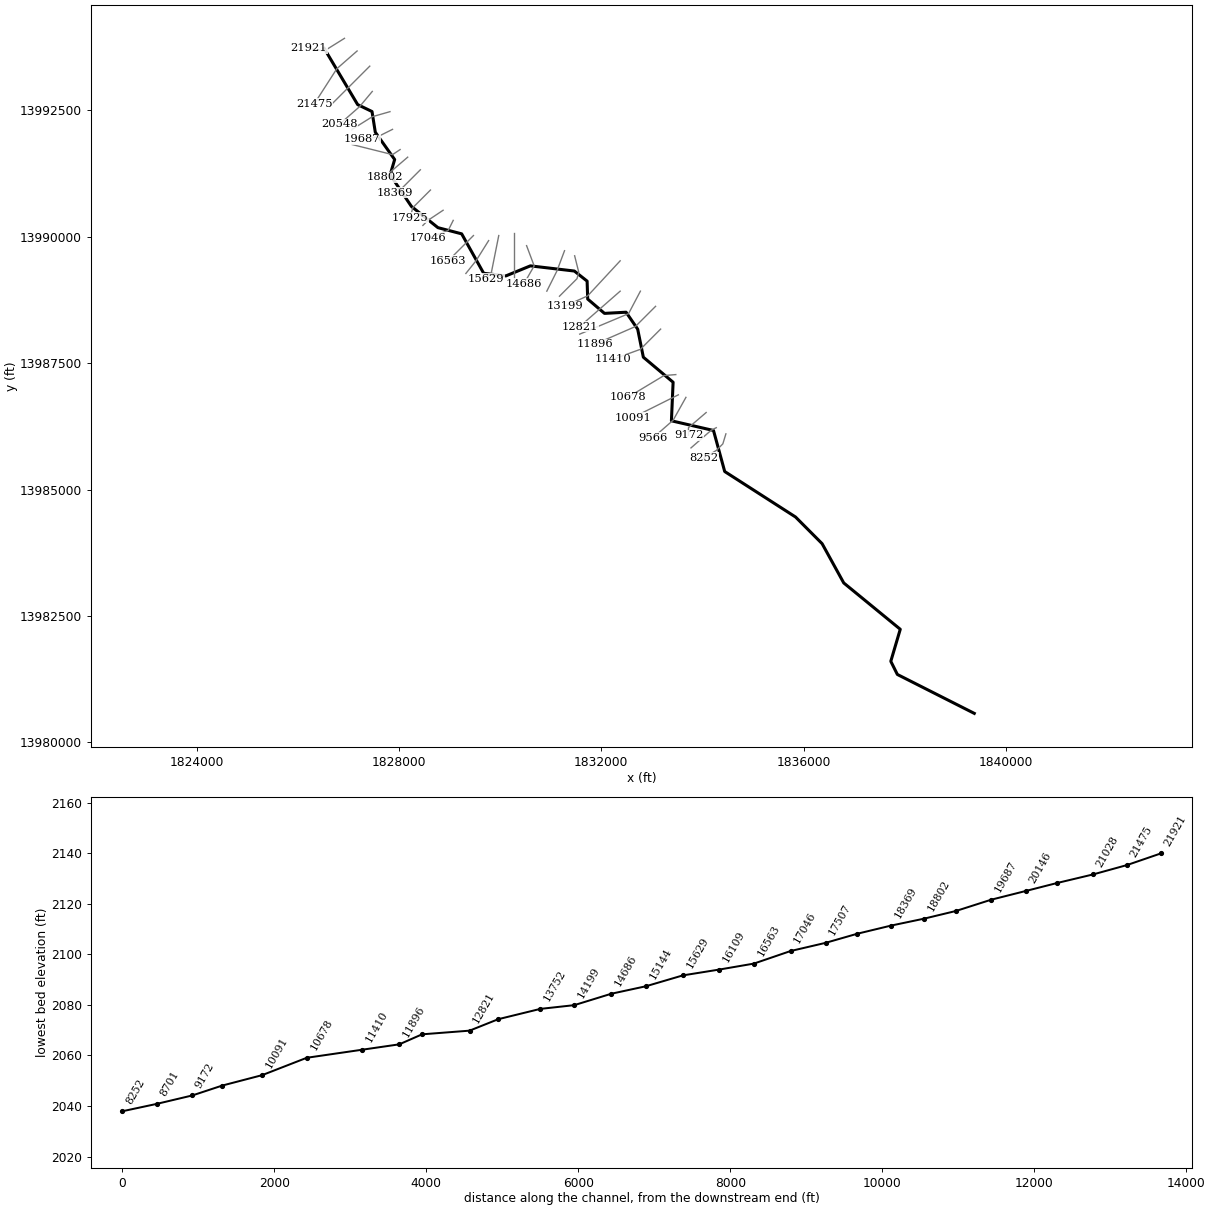
--- Stream0353.prj (project) ---

Proj Title=Stream0353 Base Level Engineering
Current Plan=p01
Default Exp/Contr=0.3,0.1
English Units
Geom File=g01
Flow File=f01
Plan File=p01
BEGIN DESCRIPTION:
Stream0353
END DESCRIPTION:

--- Stream0353.p01 (plan) ---

Plan Title=Multiple Run
Short Identifier=Multiple
Geom File=g01
Flow File=f01
Subcritical Flow
K Sum by GR= 0
Std Step Tol= 0.01
Critical Tol= 0.01
Num of Std Step Trials= 20
Max Error Tol= 0.3
Flow Tol Ratio= 0.001
Split Flow NTrial= 30
Split Flow Tol= 0.02
Split Flow Ratio= 0.02
Log Output Level= 0
Friction Slope Method= 1
Unsteady Friction Slope Method= 2
Unsteady Bridges Friction Slope Method= 1
Parabolic Critical Depth
Global Vel Dist=  1 , 1 , 1
Global Log Level= 0
CheckData=True
Encroach Param= -1, 0, 0, 0
BEGIN DESCRIPTION:
Multiple Run
END DESCRIPTION:

--- Stream0353.f01 (steady flow) ---

Flow Title=Multiple
Number of Profiles=7
Profile Names=10-year,25-year,50-year,1pct_min,100-year,1pct_plu,500-year
River Rch & RM= Stream0353,Reach-1,21921
    1660    2882    4062    2759    5505   10983   10003
River Rch & RM= Stream0353,Reach-1,20146
    2155    3785    5375    3674    7332   14628   13503
River Rch & RM= Stream0353,Reach-1,15144
    2615    4630    6607    4536    9051   18060   16817
River Rch & RM= Stream0353,Reach-1,8701
    2703    4791    6843    4702    9382   18719   17455
River Rch & RM= Stream0353,Reach-1,6926
    4370    7903   11441    7957   15876   31677   30266
Boundary for River Rch & Prof#=Stream0353,Reach-1,1
Up Type=0
Dn Type=3
Dn Slope=0.005
Boundary for River Rch & Prof#=Stream0353,Reach-1,2
Up Type=0
Dn Type=3
Dn Slope=0.005
Boundary for River Rch & Prof#=Stream0353,Reach-1,3
Up Type=0
Dn Type=3
Dn Slope=0.005
Boundary for River Rch & Prof#=Stream0353,Reach-1,4
Up Type=0
Dn Type=3
Dn Slope=0.005
Boundary for River Rch & Prof#=Stream0353,Reach-1,5
Up Type=0
Dn Type=3
Dn Slope=0.005
Boundary for River Rch & Prof#=Stream0353,Reach-1,6
Up Type=0
Dn Type=3
Dn Slope=0.005
Boundary for River Rch & Prof#=Stream0353,Reach-1,7
Up Type=0
Dn Type=3
Dn Slope=0.005

--- Stream0353.g01 (geometry) ---

Geom Title=Existing Conditions

River Reach=Stream0353,Reach-1
Reach XY= 30
      1826525.00     13993725.00      1827185.52     13992614.51
      1827469.48     13992477.44      1827534.43     13992068.39
      1827917.23     13991528.23      1827828.17     13991226.65
      1828248.02     13990601.53      1828772.70     13990180.83
      1829241.77     13990058.57      1829676.56     13989278.76
      1830114.50     13989226.22      1830599.88     13989425.30
      1831469.14     13989322.94      1831721.47     13989123.55
      1831733.11     13988768.93      1832065.20     13988485.48
      1832491.80     13988508.59      1832721.17     13988173.42
      1832833.14     13987618.94      1833421.49     13987123.75
      1833388.17     13986361.28      1834219.83     13986169.59
      1834441.46     13985358.25      1835841.70     13984458.70
      1836367.12     13983931.13      1836794.63     13983154.53
      1837911.88     13982238.22      1837724.79     13981604.94
      1837854.53     13981344.63      1839375.00     13980575.00

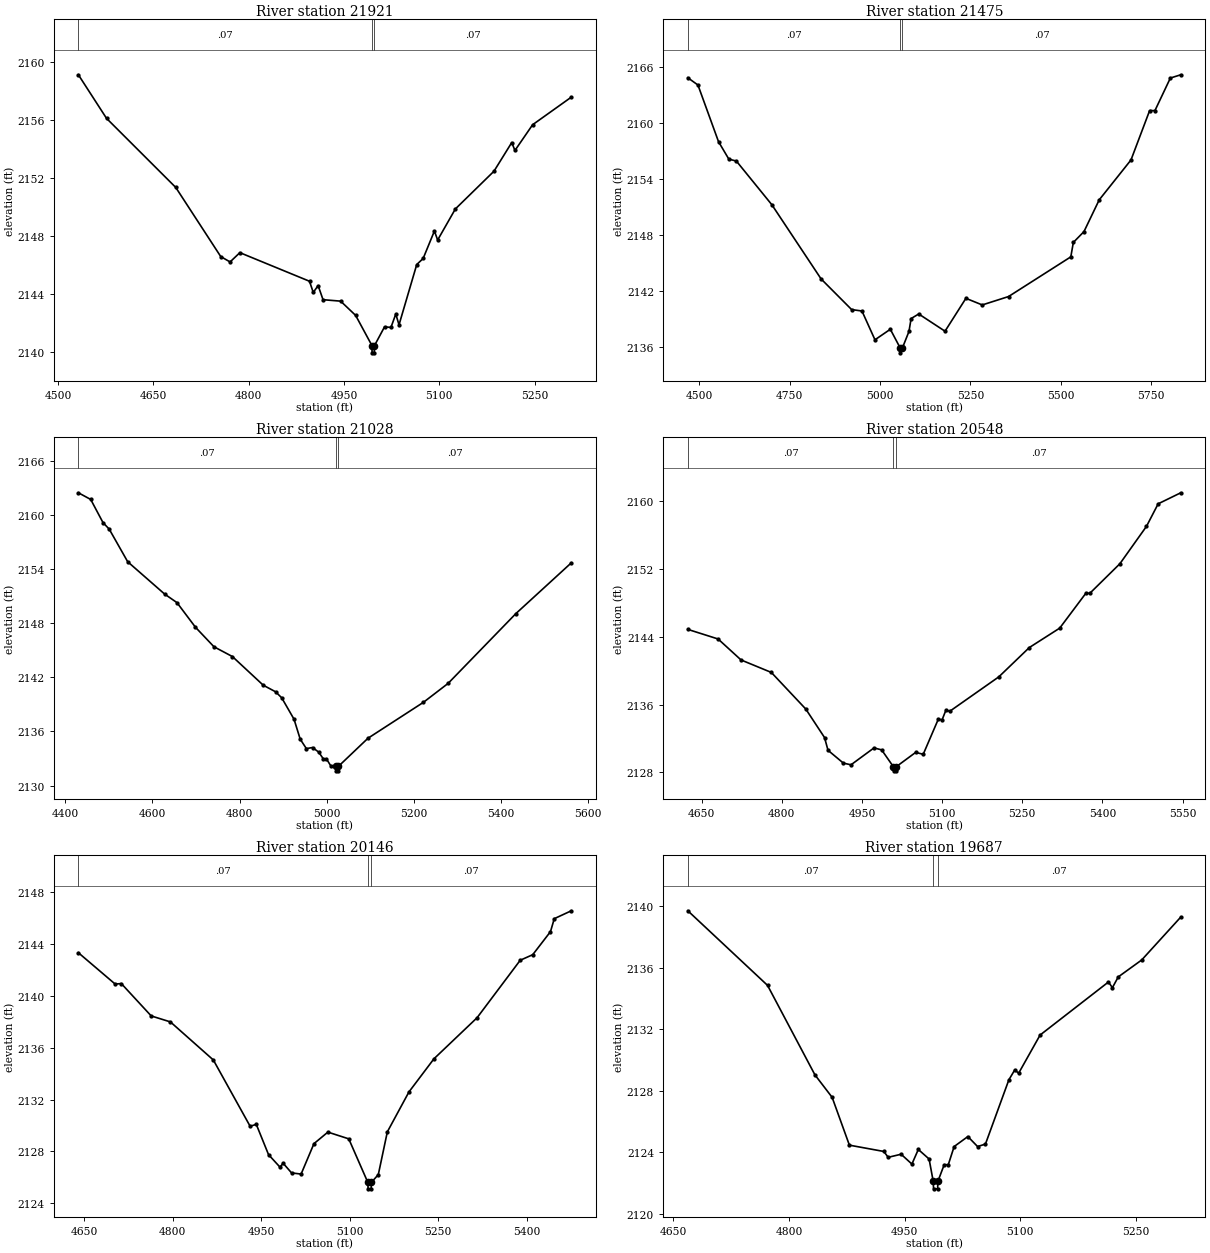
Type RM Length L Ch R = 1,21921,446,446,446
BEGIN DESCRIPTION:
Stream0353 47.0
END DESCRIPTION:
XS GIS Cut Line= 3
      1826925.03     13993925.02      1826525.00     13993675.00
      1826224.97     13993725.00
#Sta/Elev= 30
  4531.9 2159.10  4576.2 2156.10  4685.2 2151.34  4756.0 2146.58  4770.7 2146.21
  4786.1 2146.85  4895.7 2144.88  4901.6 2144.11  4909.3 2144.58  4917.0 2143.61
  4944.7 2143.51  4968.3 2142.53  4994.0 2140.45  4994.2 2139.95  4997.7 2139.95
  4998.0 2140.45  5013.8 2141.74  5023.9 2141.70  5031.5 2142.62  5036.6 2141.88
  5064.5 2146.03  5074.6 2146.45  5092.3 2148.34  5097.4 2147.72  5125.3 2149.86
  5186.1 2152.46  5214.0 2154.43  5219.1 2153.89  5246.9 2155.66  5307.8 2157.56
#Mann=3,-1,0
  4531.9    0.07       0  4994.0    0.05       0  4998.0    0.07       0
Bank Sta=4994,4998
Exp/Cntr=0.3,0.1

Type RM Length L Ch R = 1,21475,447,447,447
BEGIN DESCRIPTION:
Stream0353 46.0
END DESCRIPTION:
XS GIS Cut Line= 3
      1827175.00     13993675.00      1826775.00     13993325.00
      1826324.99     13992624.98
#Sta/Elev= 30
  4468.4 2164.86  4496.4 2164.08  4553.3 2158.00  4581.8 2156.13  4602.7 2155.92
  4700.9 2151.23  4837.1 2143.27  4921.6 2139.98  4950.1 2139.83  4986.1 2136.74
  5028.6 2137.87  5056.2 2135.84  5056.7 2135.34  5061.8 2135.84  5080.2 2137.64
  5086.1 2139.02  5107.2 2139.51  5179.9 2137.66  5237.7 2141.19  5282.9 2140.48
  5355.6 2141.38  5527.9 2145.64  5534.9 2147.19  5564.3 2148.35  5606.5 2151.76
  5694.4 2156.04  5745.9 2161.33  5760.7 2161.34  5803.3 2164.83  5832.1 2165.18
#Mann=3,-1,0
  4468.4    0.07       0  5056.2    0.05       0  5061.8    0.07       0
Bank Sta=5056.2,5061.8
Exp/Cntr=0.3,0.1

Type RM Length L Ch R = 1,21028,480,480,480
BEGIN DESCRIPTION:
Stream0353 45.0
END DESCRIPTION:
XS GIS Cut Line= 3
      1827425.03     13993375.03      1827025.00     13992975.00
      1826625.01     13992575.01
#Sta/Elev= 30
  4429.9 2162.51  4458.2 2161.77  4486.5 2159.19  4500.6 2158.48  4543.1 2154.85
  4627.9 2151.26  4656.2 2150.31  4698.6 2147.58  4741.1 2145.41  4783.5 2144.32
  4854.2 2141.14  4882.5 2140.41  4896.6 2139.74  4924.9 2137.36  4939.1 2135.14
  4953.2 2134.10  4967.3 2134.22  4981.5 2133.71  4992.1 2132.96  4999.2 2132.96
  5009.8 2132.14  5021.1 2132.13  5021.5 2131.63  5026.3 2131.63  5026.8 2132.13
  5094.6 2135.25  5221.9 2139.24  5278.5 2141.34  5434.0 2149.09  5561.3 2154.73
#Mann=3,-1,0
  4429.9    0.07       0  5021.1    0.05       0  5026.8    0.07       0
Bank Sta=5021.1,5026.8
Exp/Cntr=0.3,0.1

Type RM Length L Ch R = 1,20548,402,402,402
BEGIN DESCRIPTION:
Stream0353 44.0
END DESCRIPTION:
XS GIS Cut Line= 3
      1827474.97     13992874.96      1827225.00     13992575.00
      1826824.98     13992224.98
#Sta/Elev= 30
  4624.4 2144.85  4681.0 2143.72  4723.9 2141.25  4780.6 2139.78  4845.0 2135.47
  4880.1 2132.11  4886.6 2130.61  4915.3 2129.10  4929.6 2128.90  4972.6 2130.89
  4986.9 2130.66  5008.7 2128.69  5009.2 2128.19  5014.0 2128.19  5014.5 2128.69
  5050.5 2130.36  5064.7 2130.14  5093.2 2134.32  5099.8 2134.17  5107.4 2135.38
  5114.0 2135.19  5206.1 2139.26  5263.1 2142.71  5320.0 2145.00  5369.4 2149.15
  5376.0 2149.08  5432.5 2152.58  5482.3 2156.99  5504.1 2159.64  5546.4 2160.94
#Mann=3,-1,0
  4624.4    0.07       0  5008.7    0.05       0  5014.5    0.07       0
Bank Sta=5008.7,5014.5
Exp/Cntr=0.3,0.1

Type RM Length L Ch R = 1,20146,459,459,459
BEGIN DESCRIPTION:
Stream0353 43.0
END DESCRIPTION:
XS GIS Cut Line= 3
      1827825.03     13992475.01      1827475.00     13992375.00
      1827075.03     13992125.02
#Sta/Elev= 30
  4640.2 2143.34  4702.6 2140.92  4713.0 2140.96  4763.7 2138.46  4796.2 2138.00
  4869.0 2135.06  4931.4 2129.94  4941.8 2130.09  4962.6 2127.75  4982.1 2126.78
  4987.3 2127.09  5001.6 2126.34  5017.8 2126.25  5039.6 2128.60  5063.2 2129.49
  5098.6 2128.97  5130.9 2125.61  5131.4 2125.11  5136.5 2125.11  5137.0 2125.61
  5148.7 2126.21  5164.0 2129.51  5200.6 2132.59  5243.0 2135.15  5316.1 2138.32
  5389.3 2142.76  5410.5 2143.19  5440.6 2144.97  5447.0 2145.97  5475.9 2146.58
#Mann=3,-1,0
  4640.2    0.07       0  5130.9    0.05       0  5137.0    0.07       0
Bank Sta=5130.9,5137
Exp/Cntr=0.3,0.1

Type RM Length L Ch R = 1,19687,464,464,464
BEGIN DESCRIPTION:
Stream0353 42.0
END DESCRIPTION:
XS GIS Cut Line= 3
      1827874.97     13992124.98      1827575.00     13991975.00
      1827275.01     13991925.00
#Sta/Elev= 30
  4668.9 2139.71  4772.3 2134.86  4833.8 2129.04  4856.1 2127.58  4878.5 2124.47
  4923.2 2124.06  4928.8 2123.68  4945.6 2123.88  4959.6 2123.24  4967.9 2124.19
  4981.9 2123.57  4987.2 2122.13  4987.7 2121.63  4992.9 2121.63  4993.4 2122.13
  5001.5 2123.20  5006.8 2123.20  5014.4 2124.38  5032.2 2125.03  5044.8 2124.38
  5055.0 2124.54  5085.4 2128.72  5093.0 2129.36  5098.1 2129.15  5125.9 2131.63
  5214.6 2135.08  5219.7 2134.71  5227.3 2135.41  5257.7 2136.51  5308.4 2139.30
#Mann=3,-1,0
  4668.9    0.07       0  4987.2    0.05       0  4993.4    0.07       0
Bank Sta=4987.2,4993.4
Exp/Cntr=0.3,0.1

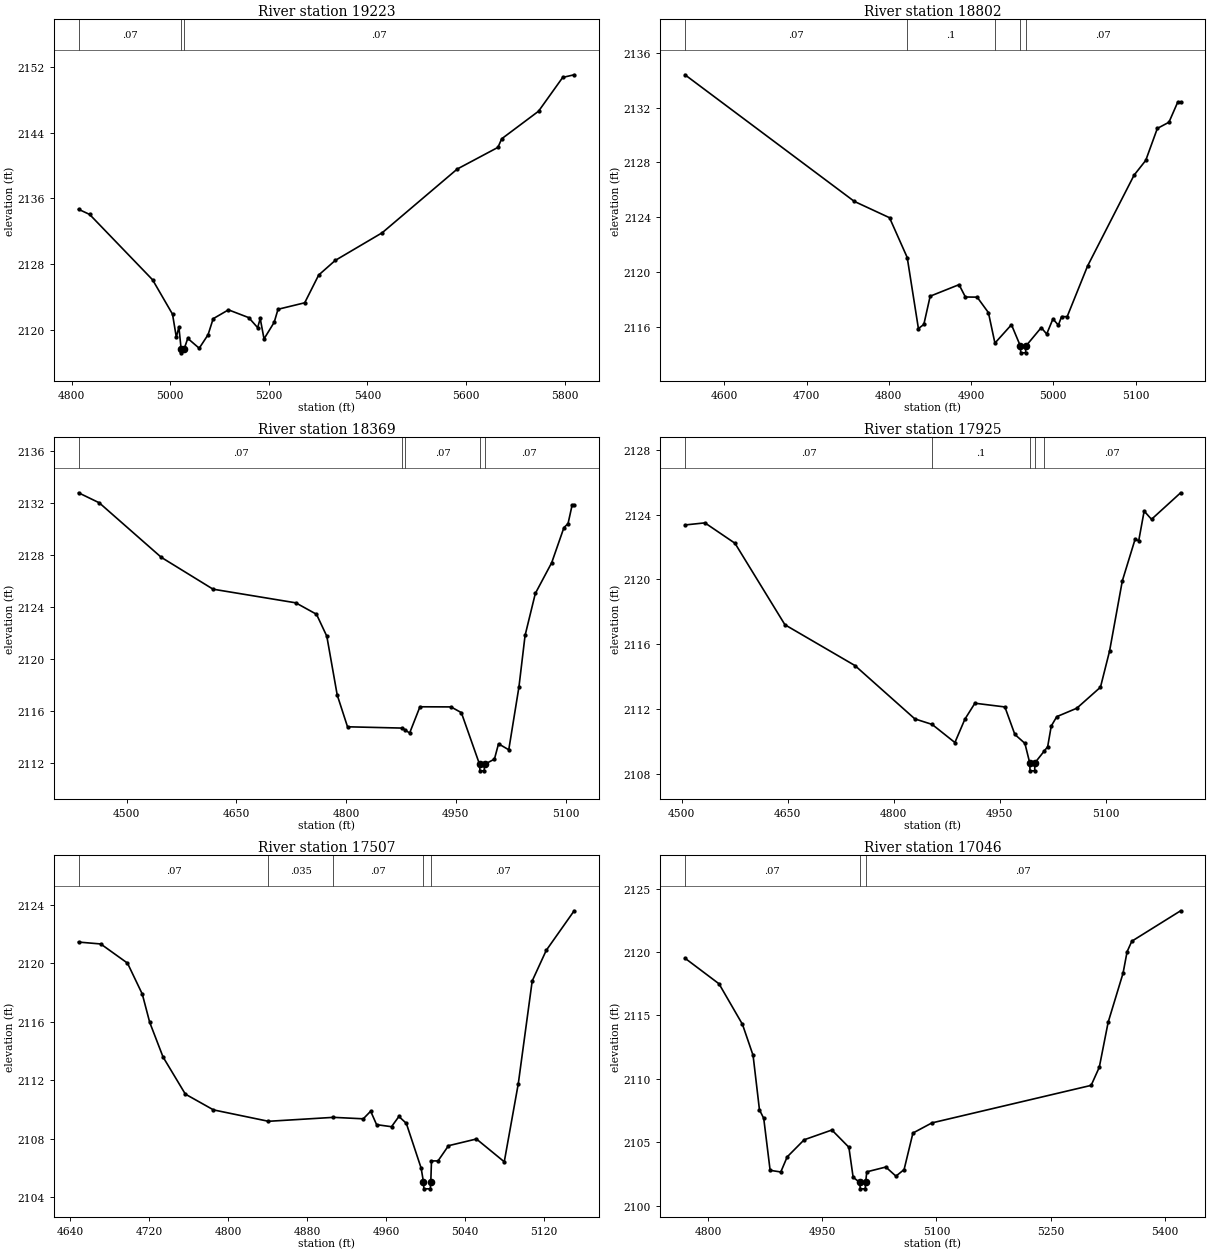
Type RM Length L Ch R = 1,19223,421,421,421
BEGIN DESCRIPTION:
Stream0353 41.0
END DESCRIPTION:
XS GIS Cut Line= 3
      1828024.99     13991725.00      1827875.00     13991625.00
      1827074.99     13991825.00
#Sta/Elev= 30
  4814.2 2134.67  4836.7 2134.04  4964.4 2126.07  5004.8 2121.88  5012.5 2119.08
  5017.7 2120.31  5022.2 2117.67  5022.7 2117.17  5028.5 2117.67  5035.7 2118.93
  5058.9 2117.73  5076.9 2119.38  5087.2 2121.33  5118.2 2122.41  5159.4 2121.46
  5177.4 2120.24  5182.6 2121.36  5190.3 2118.87  5210.9 2120.89  5218.7 2122.48
  5272.8 2123.27  5301.1 2126.65  5334.6 2128.43  5430.0 2131.81  5582.0 2139.57
  5664.5 2142.21  5672.2 2143.26  5746.9 2146.62  5795.9 2150.74  5819.1 2151.06
#Mann=3,-1,0
  4814.2    0.07       0  5022.2    0.05       0  5028.5    0.07       0
Bank Sta=5022.2,5028.5
Exp/Cntr=0.3,0.1

Type RM Length L Ch R = 1,18802,433,433,433
BEGIN DESCRIPTION:
Stream0353 40.0
END DESCRIPTION:
XS GIS Cut Line= 3
      1828174.99     13991574.99      1827825.00     13991275.00
      1827724.99     13991174.99
#Sta/Elev= 30
  4552.3 2134.39  4758.1 2125.16  4800.9 2123.97  4822.4 2121.07  4836.0 2115.89
  4842.6 2116.19  4850.3 2118.25  4885.4 2119.09  4893.1 2118.19  4907.4 2118.18
  4921.1 2117.05  4929.0 2114.83  4949.1 2116.17  4959.9 2114.62  4960.4 2114.12
  4966.2 2114.12  4966.7 2114.62  4985.3 2115.96  4991.9 2115.49  4999.5 2116.59
  5006.1 2116.14  5010.0 2116.76  5016.8 2116.76  5041.6 2120.45  5098.1 2127.07
  5112.3 2128.15  5126.4 2130.48  5140.5 2130.93  5151.2 2132.40  5154.7 2132.40
#Mann=5,-1,0
  4552.3    0.07       0  4822.4     0.1       0  4929.0    0.07       0
  4959.9    0.05       0  4966.7    0.07       0
Bank Sta=4959.9,4966.7
Exp/Cntr=0.3,0.1

Type RM Length L Ch R = 1,18369,444,444,444
BEGIN DESCRIPTION:
Stream0353 39.0
END DESCRIPTION:
XS GIS Cut Line= 3
      1828425.02     13991325.02      1828025.00     13990925.00
      1827925.01     13990875.01
#Sta/Elev= 30
  4434.3 2132.79  4462.6 2132.02  4547.5 2127.82  4618.2 2125.37  4731.3 2124.32
  4759.6 2123.44  4773.7 2121.75  4787.9 2117.23  4802.0 2114.78  4877.1 2114.68
  4881.1 2114.52  4886.9 2114.30  4901.0 2116.32  4943.4 2116.31  4957.6 2115.87
  4982.5 2111.89  4983.0 2111.39  4988.8 2111.39  4989.3 2111.89  5002.8 2112.29
  5008.4 2113.47  5022.4 2113.01  5036.3 2117.84  5044.7 2121.81  5058.7 2125.04
  5081.1 2127.41  5097.8 2130.11  5103.4 2130.41  5109.0 2131.84  5111.8 2131.84
#Mann=5,-1,0
  4434.3    0.07       0  4877.1     0.1       0  4881.1    0.07       0
  4982.5    0.05       0  4989.3    0.07       0
Bank Sta=4982.5,4989.3
Exp/Cntr=0.3,0.1

Type RM Length L Ch R = 1,17925,418,418,418
BEGIN DESCRIPTION:
Stream0353 38.0
END DESCRIPTION:
XS GIS Cut Line= 3
      1828624.97     13990924.97      1828275.00     13990575.00
      1828225.00     13990374.98
#Sta/Elev= 30
  4504.8 2123.37  4533.0 2123.50  4575.5 2122.24  4646.2 2117.20  4745.2 2114.68
  4830.0 2111.38  4854.4 2111.04  4886.6 2109.92  4900.7 2111.36  4914.9 2112.35
  4957.3 2112.12  4971.4 2110.42  4985.6 2109.87  4992.4 2108.67  4992.9 2108.17
  4999.4 2108.17  4999.9 2108.67  5012.9 2109.39  5017.8 2109.66  5022.9 2110.94
  5030.7 2111.52  5059.0 2112.04  5092.5 2113.34  5105.4 2115.58  5123.4 2119.91
  5141.5 2122.49  5146.6 2122.39  5154.3 2124.23  5164.7 2123.72  5205.9 2125.36
#Mann=5,-1,0
  4504.8    0.07       0  4854.4     0.1       0  4992.4    0.05       0
  4999.9     0.1       0  5012.9    0.07       0
Bank Sta=4992.4,4999.9
Exp/Cntr=0.3,0.1

Type RM Length L Ch R = 1,17507,461,461,461
BEGIN DESCRIPTION:
Stream0353 37.0
END DESCRIPTION:
XS GIS Cut Line= 3
      1828874.99     13990524.99      1828575.00     13990325.00
      1828474.97     13990224.97
#Sta/Elev= 30
  4648.3 2121.44  4670.8 2121.31  4697.9 2120.00  4712.9 2117.88  4720.4 2115.95
  4733.9 2113.58  4756.5 2111.04  4785.0 2109.96  4840.7 2109.18  4906.5 2109.45
  4936.7 2109.35  4944.2 2109.87  4950.2 2108.95  4965.3 2108.81  4972.8 2109.51
  4980.3 2109.04  4995.3 2105.98  4997.6 2105.06  4998.1 2104.56  5004.6 2104.56
  5005.1 2105.06  5005.8 2106.47  5012.4 2106.47  5023.0 2107.51  5051.3 2107.97
  5079.5 2106.41  5093.7 2111.75  5107.8 2118.78  5122.0 2120.87  5150.3 2123.58
#Mann=5,-1,0
  4648.3    0.07       0  4840.7   0.035       0  4906.5    0.07       0
  4997.6    0.05       0  5005.1    0.07       0
Bank Sta=4997.6,5005.1
Exp/Cntr=0.3,0.1

Type RM Length L Ch R = 1,17046,483,483,483
BEGIN DESCRIPTION:
Stream0353 36.0
END DESCRIPTION:
XS GIS Cut Line= 3
      1829075.00     13990325.01      1828975.00     13990125.00
      1828575.01     13989975.00
#Sta/Elev= 30
  4769.8 2119.51  4814.5 2117.49  4845.3 2114.29  4859.2 2111.85  4867.6 2107.55
  4873.2 2106.88  4881.6 2102.78  4895.6 2102.65  4904.0 2103.84  4926.3 2105.19
  4962.7 2105.96  4985.0 2104.60  4990.6 2102.23  4999.4 2101.82  4999.9 2101.32
  5006.5 2101.32  5007.0 2101.82  5008.5 2102.66  5033.5 2103.04  5046.8 2102.32
  5057.5 2102.84  5069.1 2105.72  5094.0 2106.52  5303.1 2109.48  5313.8 2110.91
  5325.4 2114.45  5345.0 2118.33  5350.3 2120.02  5356.5 2120.85  5420.6 2123.25
#Mann=3,-1,0
  4769.8    0.07       0  4999.4    0.05       0  5007.0    0.07       0
Bank Sta=4999.4,5007
Exp/Cntr=0.3,0.1

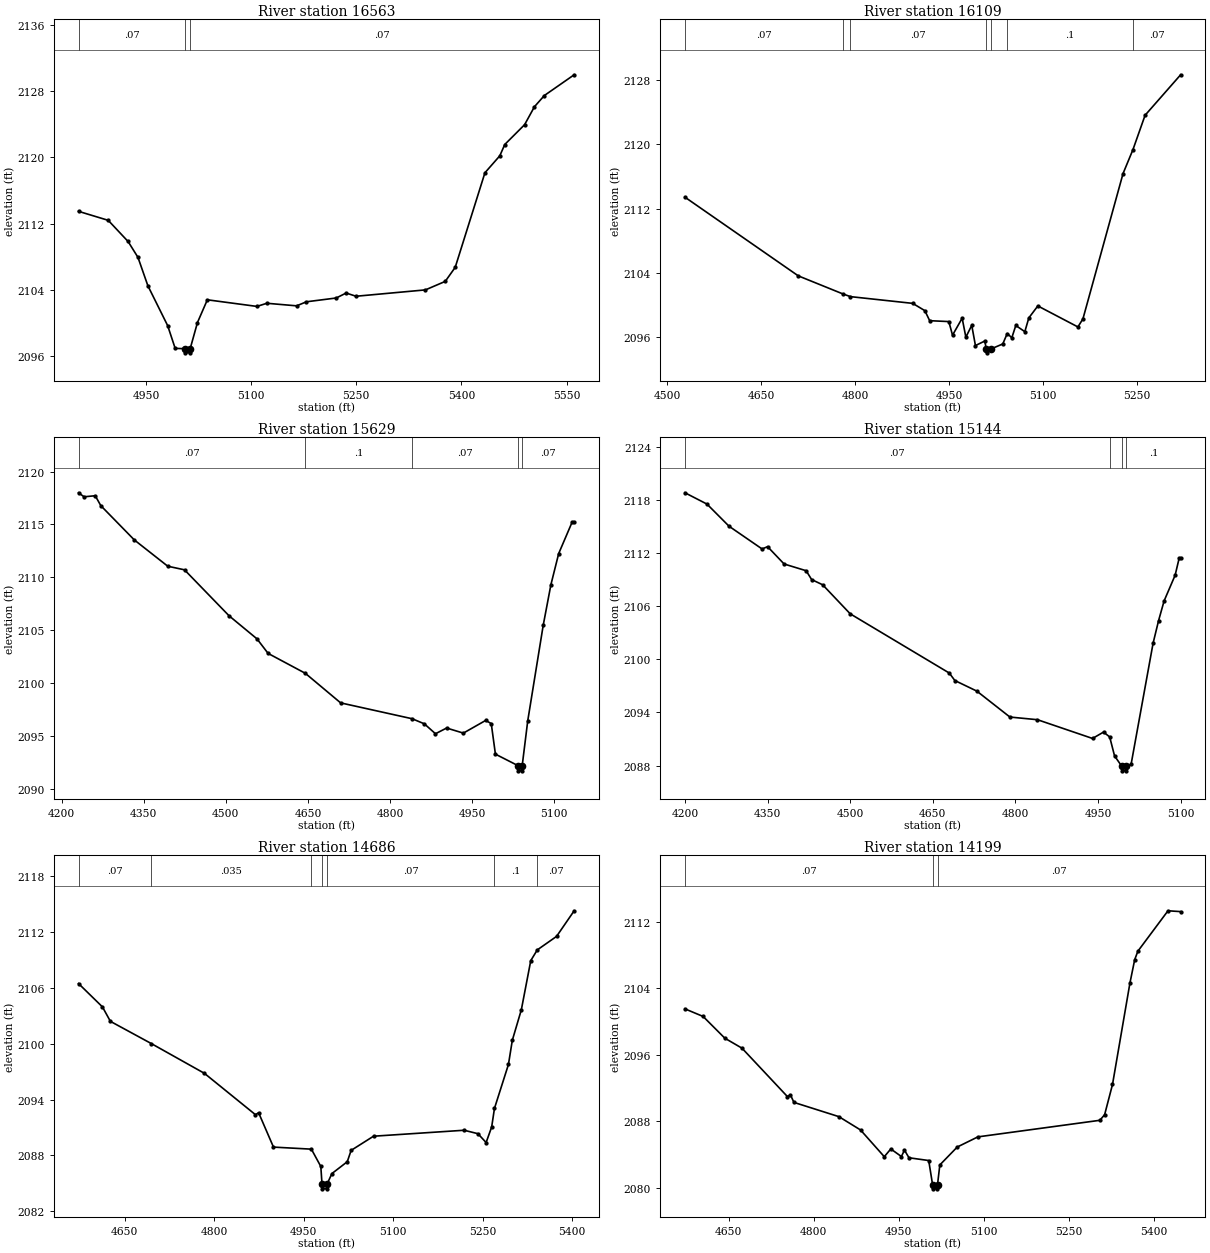
Type RM Length L Ch R = 1,16563,454,454,454
BEGIN DESCRIPTION:
Stream0353 35.0
END DESCRIPTION:
XS GIS Cut Line= 3
      1829474.98     13990024.98      1829375.00     13989925.00
      1828974.98     13989524.98
#Sta/Elev= 30
  4853.8 2113.48  4896.2 2112.39  4924.5 2109.83  4938.6 2107.91  4952.8 2104.46
  4981.0 2099.64  4991.7 2096.89  5005.5 2096.85  5006.0 2096.35  5012.6 2096.35
  5013.1 2096.85  5023.5 2100.02  5037.6 2102.77  5108.3 2101.97  5122.5 2102.35
  5164.9 2102.04  5179.0 2102.53  5221.5 2102.99  5235.6 2103.59  5249.7 2103.20
  5348.7 2103.97  5377.0 2105.00  5391.2 2106.70  5433.6 2118.15  5454.8 2120.20
  5461.9 2121.57  5490.2 2123.97  5504.3 2126.15  5518.4 2127.50  5560.9 2130.01
#Mann=3,-1,0
  4853.8    0.07       0  5005.5    0.05       0  5013.1    0.07       0
Bank Sta=5005.5,5013.1
Exp/Cntr=0.3,0.1

Type RM Length L Ch R = 1,16109,480,480,480
BEGIN DESCRIPTION:
Stream0353 34.0
END DESCRIPTION:
XS GIS Cut Line= 3
      1829774.97     13989924.96      1829525.00     13989525.00
      1829325.00     13989275.01
#Sta/Elev= 30
  4528.3 2113.41  4709.3 2103.60  4780.2 2101.36  4792.6 2101.01  4892.1 2100.17
  4911.5 2099.26  4919.2 2098.01  4949.8 2097.90  4955.7 2096.20  4971.1 2098.32
  4977.0 2095.95  4986.4 2097.43  4992.3 2094.91  5007.2 2095.47  5009.6 2094.50
  5010.1 2094.00  5017.6 2094.50  5036.0 2095.11  5043.1 2096.41  5050.4 2095.88
  5056.8 2097.41  5071.2 2096.64  5077.6 2098.36  5092.0 2099.85  5156.0 2097.23
  5164.0 2098.23  5228.1 2116.36  5244.0 2119.36  5263.3 2123.63  5320.1 2128.68
#Mann=7,-1,0
  4528.3    0.07       0  4780.2     0.1       0  4792.6    0.07       0
  5009.6    0.05       0  5017.6    0.07       0  5043.1     0.1       0
  5244.0    0.07       0
Bank Sta=5009.6,5017.6
Exp/Cntr=0.3,0.1

Type RM Length L Ch R = 1,15629,485,485,485
BEGIN DESCRIPTION:
Stream0353 33.0
END DESCRIPTION:
XS GIS Cut Line= 3
      1829975.00     13990025.00      1829825.00     13989275.00
      1829724.98     13989174.98
#Sta/Elev= 30
  4230.6 2118.00  4240.8 2117.62  4261.2 2117.72  4271.4 2116.78  4332.6 2113.54
  4393.8 2111.05  4424.4 2110.71  4505.9 2106.36  4556.9 2104.18  4577.3 2102.80
  4645.3 2100.92  4709.9 2098.12  4840.6 2096.62  4862.9 2096.14  4883.3 2095.20
  4903.7 2095.74  4934.3 2095.26  4975.1 2096.46  4985.3 2096.16  4992.9 2093.27
  5033.9 2092.19  5034.4 2091.69  5041.4 2091.69  5041.9 2092.19  5052.0 2096.42
  5080.3 2105.46  5094.4 2109.31  5108.6 2112.25  5133.3 2115.24  5136.9 2115.24
#Mann=5,-1,0
  4230.6    0.07       0  4645.3     0.1       0  4840.6    0.07       0
  5033.9    0.05       0  5041.9    0.07       0
Bank Sta=5033.9,5041.9
Exp/Cntr=0.3,0.1

Type RM Length L Ch R = 1,15144,458,458,458
BEGIN DESCRIPTION:
Stream0353 32.0
END DESCRIPTION:
XS GIS Cut Line= 3
      1830275.00     13990074.98      1830275.00     13989275.00
      1830275.00     13989174.98
#Sta/Elev= 30
  4200.1 2118.83  4240.1 2117.55  4280.1 2115.05  4340.1 2112.48  4350.1 2112.74
  4380.1 2110.78  4420.1 2110.02  4430.1 2109.02  4450.1 2108.43  4500.1 2105.15
  4680.1 2098.45  4690.1 2097.61  4730.1 2096.41  4790.1 2093.48  4840.1 2093.18
  4940.1 2091.06  4960.1 2091.78  4971.3 2091.23  4980.1 2089.09  4993.4 2087.90
  4993.9 2087.40  5001.2 2087.40  5001.7 2087.90  5010.1 2088.12  5050.1 2101.83
  5060.1 2104.39  5070.1 2106.61  5090.1 2109.51  5097.6 2111.48  5100.1 2111.48
#Mann=4,-1,0
  4200.1    0.07       0  4971.3     0.1       0  4993.4    0.05       0
  5001.7     0.1       0
Bank Sta=4993.4,5001.7
Exp/Cntr=0.3,0.1

Type RM Length L Ch R = 1,14686,487,487,487
BEGIN DESCRIPTION:
Stream0353 31.0
END DESCRIPTION:
XS GIS Cut Line= 3
      1830525.00     13989825.01      1830675.00     13989425.00
      1830475.01     13989075.02
#Sta/Elev= 30
  4572.9 2106.46  4613.0 2103.95  4626.3 2102.40  4694.7 2100.02  4783.8 2096.82
  4869.3 2092.38  4874.6 2092.59  4899.5 2088.90  4963.0 2088.68  4978.8 2086.82
  4980.8 2084.92  4981.3 2084.42  4988.7 2084.42  4989.2 2084.92  4997.4 2086.06
  5023.1 2087.33  5029.6 2088.55  5067.1 2090.07  5218.9 2090.71  5242.0 2090.34
  5255.7 2089.39  5265.0 2091.06  5269.7 2093.06  5293.1 2097.77  5299.6 2100.37
  5314.7 2103.64  5330.5 2108.92  5341.4 2110.07  5373.7 2111.52  5403.2 2114.27
#Mann=7,-1,0
  4572.9    0.07       0  4694.7   0.035       0  4963.0    0.07       0
  4980.8    0.05       0  4989.2    0.07       0  5269.7     0.1       0
  5341.4    0.07       0
Bank Sta=4980.8,4989.2
Exp/Cntr=0.3,0.1

Type RM Length L Ch R = 1,14199,447,447,447
BEGIN DESCRIPTION:
Stream0353 30.0
END DESCRIPTION:
XS GIS Cut Line= 3
      1831275.00     13989725.01      1831125.00     13989325.00
      1830925.01     13988925.02
#Sta/Elev= 30
  4572.8 2101.52  4604.8 2100.61  4643.1 2098.00  4673.4 2096.80  4753.5 2090.99
  4758.8 2091.20  4765.0 2090.29  4844.3 2088.58  4882.5 2086.98  4924.4 2083.77
  4935.9 2084.70  4954.6 2083.79  4960.0 2084.56  4968.0 2083.64  5002.8 2083.31
  5009.6 2080.41  5010.1 2079.91  5017.8 2079.91  5018.3 2080.41  5022.4 2082.78
  5053.1 2084.93  5089.5 2086.15  5304.7 2088.14  5313.1 2088.81  5327.0 2092.44
  5357.8 2104.64  5366.2 2107.44  5371.8 2108.45  5424.9 2113.30  5447.2 2113.20
#Mann=3,-1,0
  4572.8    0.07       0  5009.6    0.05       0  5018.3    0.07       0
Bank Sta=5009.6,5018.3
Exp/Cntr=0.3,0.1

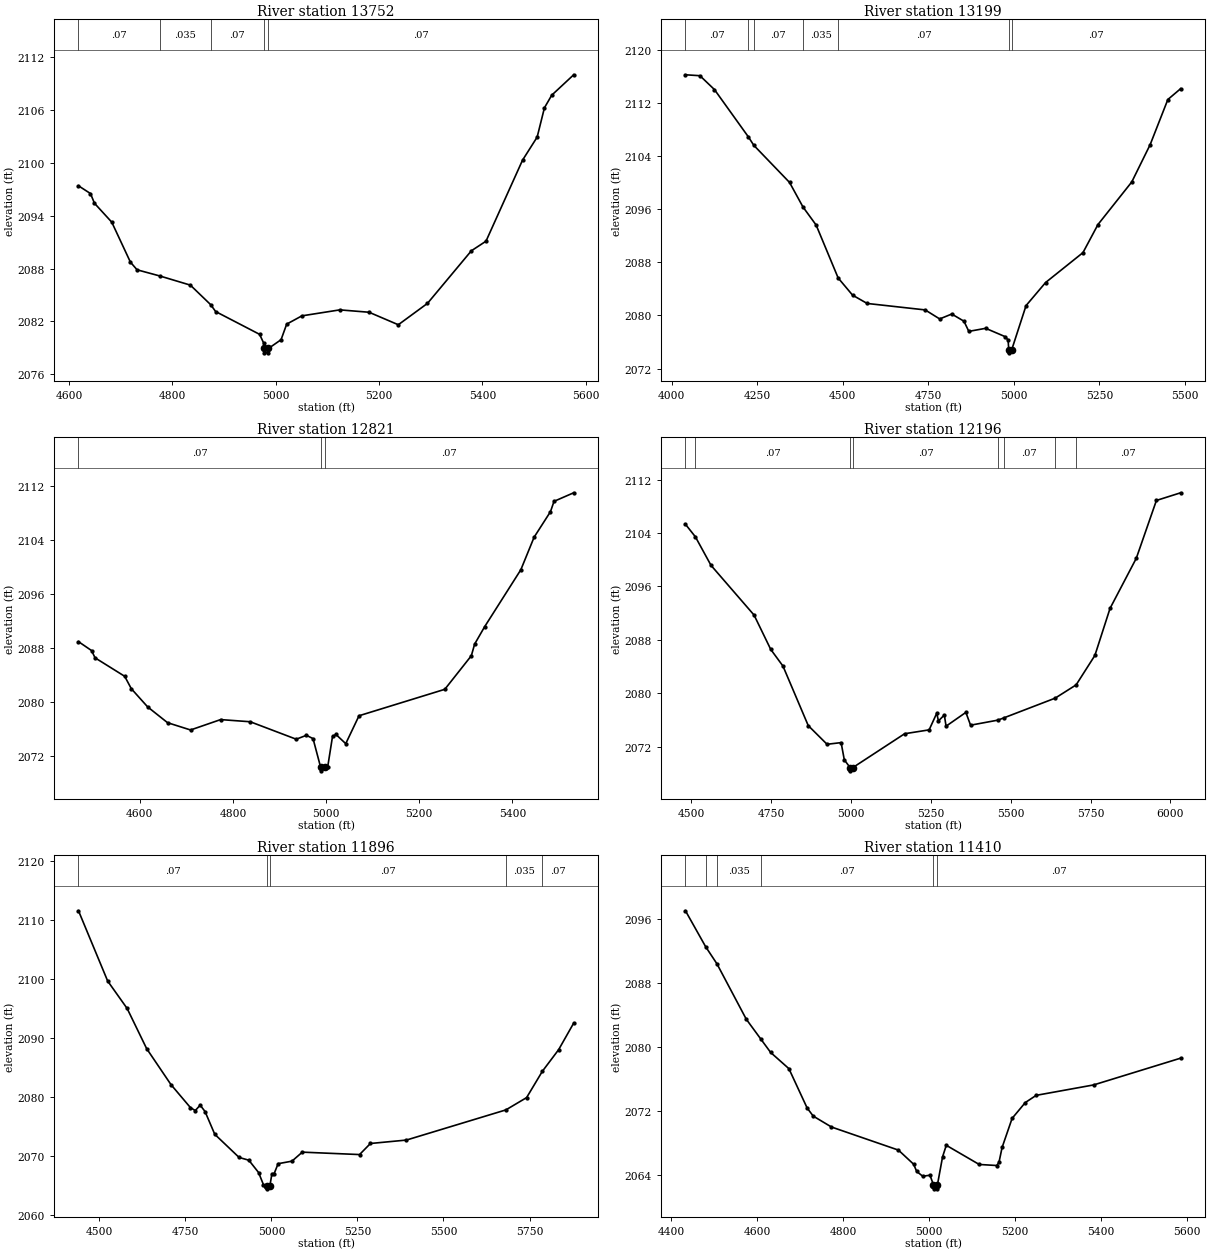
Type RM Length L Ch R = 1,13752,553,553,553
BEGIN DESCRIPTION:
Stream0353 29.0
END DESCRIPTION:
XS GIS Cut Line= 4
      1831475.00     13989625.00      1831556.47     13989299.13
      1831521.58     13989171.58      1831174.98     13988824.98
#Sta/Elev= 30
  4618.5 2097.40  4641.7 2096.52  4649.4 2095.42  4682.9 2093.27  4719.0 2088.73
  4731.9 2087.86  4775.9 2087.16  4835.0 2086.12  4874.3 2083.90  4883.9 2083.12
  4969.0 2080.53  4976.6 2079.57  4977.4 2078.93  4977.9 2078.43  4985.7 2078.43
  4986.2 2078.93  5010.5 2079.92  5021.4 2081.69  5050.8 2082.63  5124.2 2083.31
  5180.8 2083.04  5237.4 2081.62  5293.9 2084.05  5378.8 2090.02  5407.1 2091.11
  5477.8 2100.31  5506.1 2102.93  5520.2 2106.26  5534.3 2107.69  5576.8 2110.01
#Mann=5,-1,0
  4618.5    0.07       0  4775.9   0.035       0  4874.3    0.07       0
  4977.4    0.05       0  4986.2    0.07       0
Bank Sta=4977.4,4986.2
Exp/Cntr=0.3,0.1

Type RM Length L Ch R = 1,13199,378,378,378
BEGIN DESCRIPTION:
Stream0353 28.0
END DESCRIPTION:
XS GIS Cut Line= 3
      1832375.01     13989525.01      1831734.15     13988833.22
      1831274.97     13988624.99
#Sta/Elev= 30
  4040.4 2116.20  4082.7 2116.06  4125.2 2113.97  4224.2 2106.86  4240.1 2105.59
  4344.6 2100.00  4383.8 2096.31  4422.3 2093.59  4486.7 2085.62  4528.8 2083.04
  4571.4 2081.79  4740.9 2080.82  4783.4 2079.46  4818.6 2080.20  4854.3 2079.12
  4868.5 2077.59  4917.8 2078.05  4974.5 2076.80  4983.4 2076.28  4985.1 2074.86
  4985.6 2074.36  4994.1 2074.86  5035.8 2081.47  5092.9 2084.94  5202.1 2089.44
  5246.0 2093.67  5344.8 2100.08  5398.5 2105.69  5450.2 2112.48  5487.6 2114.11
#Mann=7,-1,0
  4040.4    0.07       0  4224.2   0.035       0  4240.1    0.07       0
  4383.8   0.035       0  4486.7    0.07       0  4985.1    0.05       0
  4994.1    0.07       0
Bank Sta=4985.1,4994.1
Exp/Cntr=0.3,0.1

Type RM Length L Ch R = 1,12821,625,625,625
BEGIN DESCRIPTION:
Stream0353 27.0
END DESCRIPTION:
XS GIS Cut Line= 3
      1832374.99     13988924.99      1831975.00     13988575.00
      1831575.00     13988225.00
#Sta/Elev= 30
  4468.5 2088.98  4496.5 2087.66  4504.1 2086.58  4567.7 2083.84  4581.9 2082.00
  4617.0 2079.30  4659.7 2076.96  4709.1 2075.88  4773.6 2077.42  4837.2 2077.10
  4935.9 2074.51  4957.8 2075.09  4972.0 2074.60  4988.4 2070.32  4988.9 2069.82
  4997.4 2070.32  5003.3 2070.34  5013.8 2074.92  5021.3 2075.21  5042.2 2073.85
  5070.7 2077.99  5254.8 2081.91  5311.8 2086.89  5318.9 2088.62  5340.3 2091.19
  5418.1 2099.65  5446.6 2104.48  5481.7 2108.26  5489.3 2109.79  5531.5 2111.06
#Mann=3,-1,0
  4468.5    0.07       0  4988.4    0.05       0  4997.4    0.07       0
Bank Sta=4988.4,4997.4
Exp/Cntr=0.3,0.1

Type RM Length L Ch R = 1,12196,300,300,300
BEGIN DESCRIPTION:
Stream0353 26.0
END DESCRIPTION:
XS GIS Cut Line= 3
      1832775.00     13988925.00      1832540.65     13988480.14
      1831575.01     13988075.00
#Sta/Elev= 30
  4481.8 2105.32  4512.9 2103.44  4561.7 2099.17  4696.6 2091.71  4748.7 2086.57
  4787.0 2084.07  4866.1 2075.15  4925.0 2072.35  4969.0 2072.60  4979.0 2070.02
  4997.0 2068.87  4997.5 2068.37  5006.1 2068.87  5167.8 2073.93  5244.5 2074.51
  5268.3 2077.00  5273.7 2075.85  5292.1 2076.74  5297.5 2075.06  5359.5 2077.13
  5374.2 2075.21  5459.8 2075.97  5477.4 2076.29  5638.9 2079.26  5704.6 2081.25
  5763.3 2085.66  5810.8 2092.72  5893.0 2100.23  5955.9 2108.89  6031.8 2110.04
#Mann=8,-1,0
  4481.8     0.1       0  4512.9    0.07       0  4997.0    0.05       0
  5006.1    0.07       0  5459.8   0.035       0  5477.4    0.07       0
  5638.9   0.035       0  5704.6    0.07       0
Bank Sta=4997,5006.1
Exp/Cntr=0.3,0.1

Type RM Length L Ch R = 1,11896,486,486,486
BEGIN DESCRIPTION:
Stream0353 25.0
END DESCRIPTION:
XS GIS Cut Line= 3
      1833075.00     13988625.00      1832675.00     13988225.00
      1831875.00     13987875.00
#Sta/Elev= 30
  4439.4 2111.62  4524.2 2099.69  4580.8 2095.03  4637.4 2088.22  4708.1 2082.11
  4764.7 2078.20  4778.8 2077.70  4793.0 2078.62  4807.1 2077.54  4835.4 2073.67
  4906.1 2069.74  4934.4 2069.27  4962.7 2067.18  4976.8 2065.12  4986.4 2064.91
  4986.9 2064.41  4995.5 2064.91  5001.5 2066.98  5007.8 2066.98  5019.5 2068.68
  5059.7 2069.11  5089.7 2070.64  5256.1 2070.23  5287.7 2072.11  5392.2 2072.69
  5681.2 2077.81  5741.5 2079.90  5787.3 2084.37  5834.6 2088.04  5878.3 2092.55
#Mann=5,-1,0
  4439.4    0.07       0  4986.4    0.05       0  4995.5    0.07       0
  5681.2   0.035       0  5787.3    0.07       0
Bank Sta=4986.4,4995.5
Exp/Cntr=0.3,0.1

Type RM Length L Ch R = 1,11410,732,732,732
BEGIN DESCRIPTION:
Stream0353 24.0
END DESCRIPTION:
XS GIS Cut Line= 3
      1833174.99     13988174.99      1832775.00     13987775.00
      1832225.00     13987575.00
#Sta/Elev= 30
  4433.9 2096.97  4480.8 2092.49  4507.0 2090.36  4575.3 2083.44  4608.5 2081.01
  4631.9 2079.30  4674.3 2077.28  4716.7 2072.37  4730.9 2071.36  4773.3 2070.00
  4928.9 2067.12  4964.2 2065.36  4971.3 2064.46  4985.4 2063.86  5002.2 2063.99
  5010.3 2062.79  5010.8 2062.29  5019.0 2062.29  5019.5 2062.79  5031.5 2066.29
  5040.1 2067.72  5116.6 2065.33  5157.2 2065.20  5162.5 2065.58  5169.8 2067.45
  5193.1 2071.08  5223.7 2073.05  5249.0 2073.95  5382.6 2075.25  5584.8 2078.59
#Mann=6,-1,0
  4433.9   0.035       0  4480.8    0.07       0  4507.0   0.035       0
  4608.5    0.07       0  5010.3    0.05       0  5019.5    0.07       0
Bank Sta=5010.3,5019.5
Exp/Cntr=0.3,0.1

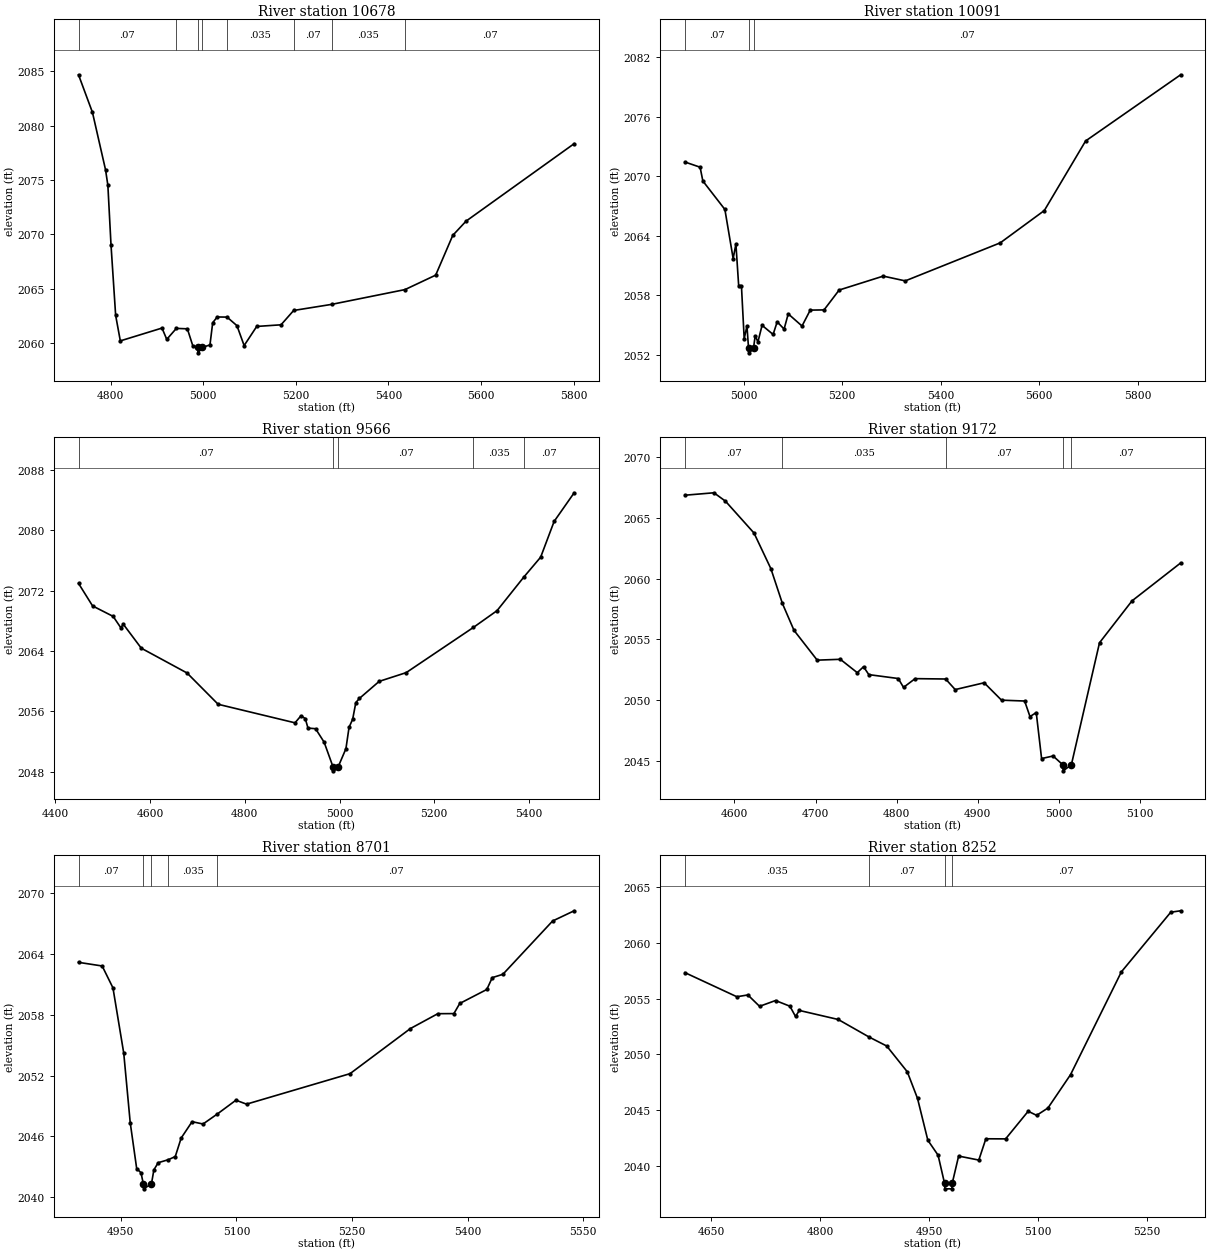
Type RM Length L Ch R = 1,10678,587,587,587
BEGIN DESCRIPTION:
Stream0353 23.0
END DESCRIPTION:
XS GIS Cut Line= 3
      1833474.96     13987275.00      1833240.68     13987255.94
      1832524.97     13986824.98
#Sta/Elev= 30
  4730.5 2084.68  4760.6 2081.22  4788.9 2075.93  4793.9 2074.51  4800.7 2069.01
  4810.7 2062.54  4820.8 2060.19  4910.8 2061.37  4921.1 2060.33  4941.8 2061.34
  4965.6 2061.30  4977.5 2059.72  4988.0 2059.59  4988.5 2059.09  4998.1 2059.59
  5014.4 2059.82  5020.3 2061.86  5030.0 2062.39  5051.3 2062.38  5072.7 2061.59
  5088.2 2059.76  5115.4 2061.52  5167.9 2061.67  5195.2 2062.99  5277.2 2063.55
  5435.6 2064.91  5501.9 2066.24  5538.8 2069.90  5567.5 2071.21  5801.0 2078.34
#Mann=8,-1,0
  4730.5    0.07       0  4941.8   0.035       0  4988.0    0.05       0
  4998.1   0.035       0  5051.3   0.035       0  5195.2    0.07       0
  5277.2   0.035       0  5435.6    0.07       0
Bank Sta=4988,4998.1
Exp/Cntr=0.3,0.1

Type RM Length L Ch R = 1,10091,525,525,525
BEGIN DESCRIPTION:
Stream0353 22.0
END DESCRIPTION:
XS GIS Cut Line= 3
      1833524.98     13986874.99      1833425.00     13986825.00
      1832625.01     13986425.00
#Sta/Elev= 30
  4881.1 2071.42  4911.8 2070.90  4917.4 2069.51  4962.1 2066.65  4978.9 2061.71
  4984.5 2063.17  4990.1 2058.98  4995.7 2058.98  5001.3 2053.64  5006.9 2054.92
  5010.1 2052.72  5010.6 2052.22  5020.3 2052.72  5023.6 2053.93  5029.2 2053.32
  5037.6 2054.99  5060.0 2054.07  5068.3 2055.34  5082.3 2054.61  5090.7 2056.14
  5118.7 2054.92  5135.4 2056.52  5163.4 2056.54  5194.1 2058.54  5283.6 2059.94
  5328.3 2059.46  5521.2 2063.29  5610.6 2066.54  5694.4 2073.54  5887.3 2080.20
#Mann=3,-1,0
  4881.1    0.07       0  5010.1    0.05       0  5020.3    0.07       0
Bank Sta=5010.1,5020.3
Exp/Cntr=0.3,0.1

Type RM Length L Ch R = 1,9566,394,394,394
BEGIN DESCRIPTION:
Stream0353 21.0
END DESCRIPTION:
XS GIS Cut Line= 3
      1833674.99     13986824.98      1833422.14     13986372.43
      1833024.97     13986024.98
#Sta/Elev= 30
  4449.1 2072.97  4478.8 2069.98  4522.2 2068.59  4538.2 2067.10  4543.9 2067.53
  4581.6 2064.37  4678.2 2061.08  4743.8 2056.93  4906.0 2054.47  4918.7 2055.41
  4927.7 2055.03  4933.4 2053.77  4949.4 2053.69  4967.5 2051.90  4986.4 2048.60
  4986.9 2048.10  4996.9 2048.60  5013.5 2051.04  5020.1 2053.88  5027.7 2054.94
  5034.4 2057.16  5042.0 2057.71  5083.7 2059.97  5140.7 2061.13  5282.6 2067.13
  5332.4 2069.35  5389.1 2073.82  5424.5 2076.45  5452.9 2081.19  5495.2 2084.99
#Mann=5,-1,0
  4449.1    0.07       0  4986.4    0.05       0  4996.9    0.07       0
  5282.6   0.035       0  5389.1    0.07       0
Bank Sta=4986.4,4996.9
Exp/Cntr=0.3,0.1

Type RM Length L Ch R = 1,9172,471,471,471
BEGIN DESCRIPTION:
Stream0353 20.0
END DESCRIPTION:
XS GIS Cut Line= 3
      1834074.99     13986524.99      1833725.00     13986225.00
      1833725.00     13986074.97
#Sta/Elev= 30
  4539.0 2066.85  4574.7 2067.05  4588.9 2066.36  4624.1 2063.74  4644.9 2060.81
  4659.1 2057.95  4673.4 2055.74  4702.0 2053.29  4730.5 2053.36  4751.4 2052.26
  4759.1 2052.75  4765.6 2052.10  4801.9 2051.78  4808.4 2051.05  4822.7 2051.77
  4860.3 2051.74  4872.1 2050.87  4907.8 2051.43  4929.2 2050.00  4957.7 2049.93
  4964.3 2048.65  4972.0 2048.98  4978.6 2045.20  4992.8 2045.41  5004.7 2044.69
  5005.2 2044.19  5015.3 2044.69  5050.0 2054.72  5090.0 2058.16  5150.0 2061.28
#Mann=5,-1,0
  4539.0    0.07       0  4659.1   0.035       0  4860.3    0.07       0
  5004.7    0.05       0  5015.3    0.07       0
Bank Sta=5004.7,5015.3
Exp/Cntr=0.3,0.1

Type RM Length L Ch R = 1,8701,449,449,449
BEGIN DESCRIPTION:
Stream0353 19.0
END DESCRIPTION:
XS GIS Cut Line= 3
      1834275.00     13986225.00      1834175.00     13986175.00
      1833775.00     13985825.00
#Sta/Elev= 30
  4895.1 2063.19  4925.8 2062.83  4939.8 2060.67  4953.8 2054.23  4962.2 2047.37
  4970.6 2042.83  4976.2 2042.42  4979.2 2041.33  4979.7 2040.83  4989.8 2041.33
  4992.9 2042.70  4998.5 2043.41  5011.8 2043.71  5020.7 2044.02  5028.3 2045.84
  5042.5 2047.46  5056.7 2047.23  5075.3 2048.22  5099.4 2049.58  5113.2 2049.19
  5247.5 2052.20  5325.8 2056.65  5361.4 2058.12  5382.3 2058.13  5389.9 2059.13
  5425.0 2060.51  5432.1 2061.68  5445.9 2062.01  5510.4 2067.27  5538.4 2068.28
#Mann=5,-1,0
  4895.1    0.07       0  4979.2    0.05       0  4989.8    0.07       0
  5011.8   0.035       0  5075.3    0.07       0
Bank Sta=4979.2,4989.8
Exp/Cntr=0.3,0.1

Type RM Length L Ch R = 1,8252,444,444,444
BEGIN DESCRIPTION:
Stream0353 18.0
END DESCRIPTION:
XS GIS Cut Line= 4
      1834465.14     13986103.26      1834404.52     13985904.52
      1834275.00     13985775.00      1834024.99     13985625.00
#Sta/Elev= 30
  4613.6 2057.33  4685.0 2055.17  4700.2 2055.33  4716.3 2054.31  4738.3 2054.83
  4758.1 2054.32  4765.8 2053.40  4771.1 2053.94  4824.6 2053.13  4867.0 2051.56
  4891.4 2050.75  4919.7 2048.44  4933.8 2046.05  4948.0 2042.30  4962.1 2040.96
  4971.0 2038.44  4971.5 2037.94  4981.1 2037.94  4981.6 2038.44  4990.4 2040.88
  5018.2 2040.52  5027.9 2042.43  5055.1 2042.42  5086.2 2044.90  5097.8 2044.53
  5113.4 2045.19  5144.5 2048.18  5214.5 2057.40  5282.5 2062.75  5296.1 2062.88
#Mann=4,-1,0
  4613.6   0.035       0  4867.0    0.07       0  4971.0    0.05       0
  4981.6    0.07       0
Bank Sta=4971,4981.6
Exp/Cntr=0.3,0.1