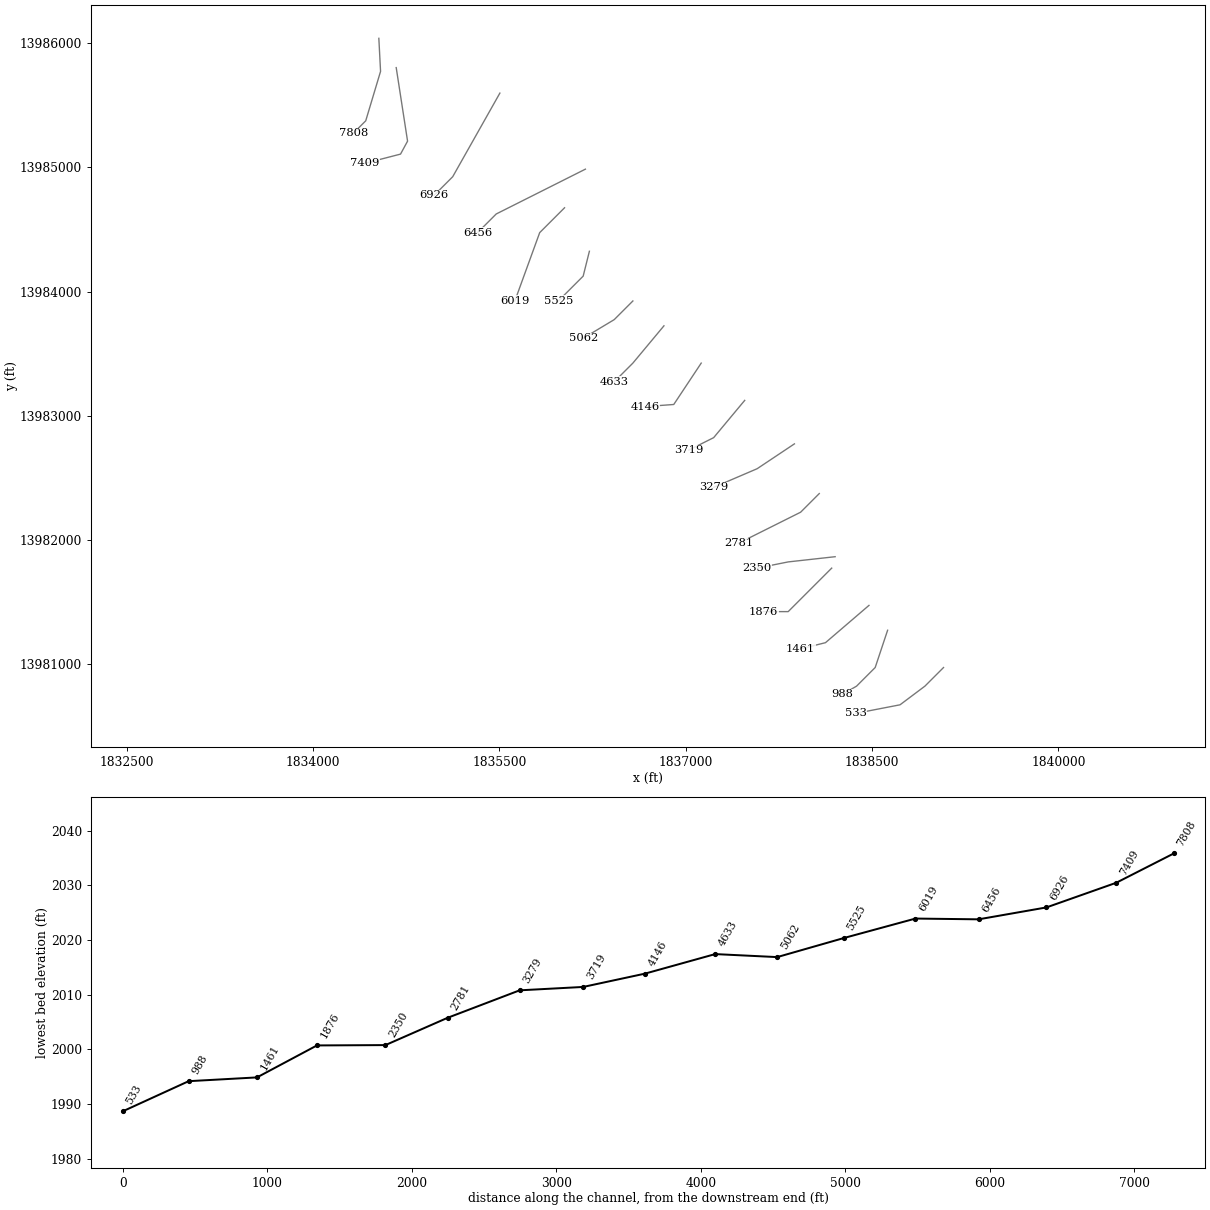
HEC-RAS study Stream0353.prj: Stream0353 Base Level Engineering

--- Stream0353.g01 (geometry) --- (continued)

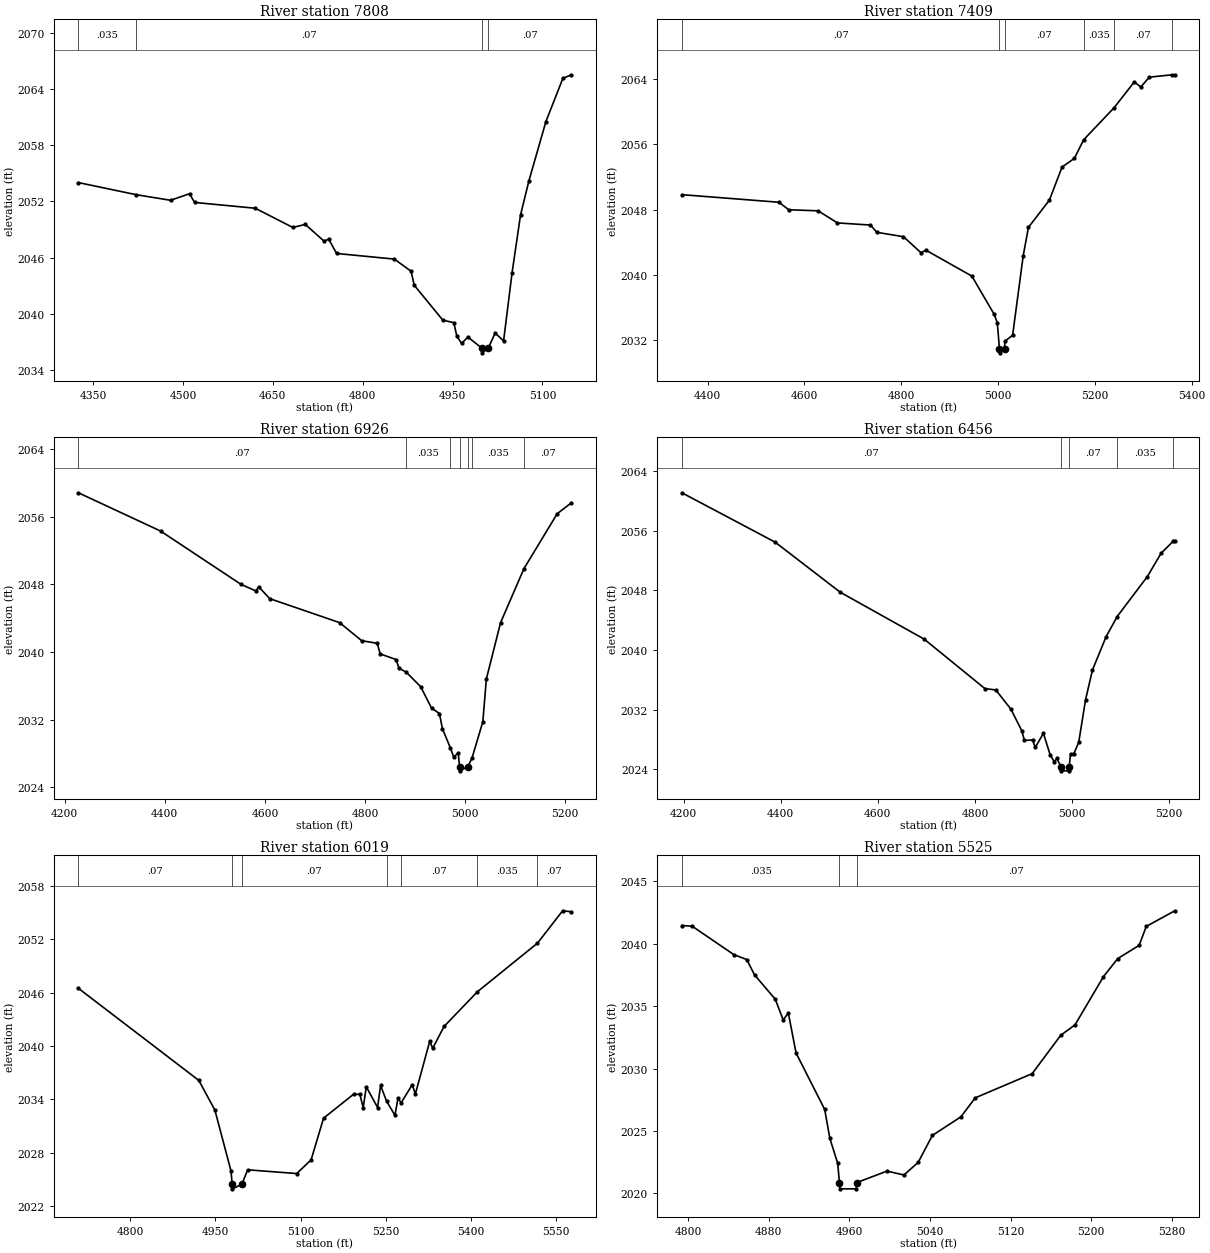
Type RM Length L Ch R = 1,7808,399,399,399
BEGIN DESCRIPTION:
Stream0353 17.0
END DESCRIPTION:
XS GIS Cut Line= 4
      1834530.52     13986038.65      1834544.36     13985772.87
      1834425.00     13985375.00      1834325.03     13985275.03
#Sta/Elev= 30
  4325.4 2054.02  4422.4 2052.72  4479.3 2052.13  4511.0 2052.83  4519.3 2051.90
  4620.6 2051.28  4683.3 2049.23  4704.2 2049.55  4735.5 2047.77  4743.3 2047.98
  4756.4 2046.45  4852.9 2045.85  4880.8 2044.55  4886.0 2043.06  4933.8 2039.33
  4952.1 2039.06  4957.3 2037.60  4965.2 2036.85  4975.6 2037.53  4999.0 2036.34
  4999.5 2035.84  5009.7 2036.34  5021.1 2037.96  5035.2 2037.11  5049.4 2044.40
  5063.5 2050.56  5077.6 2054.23  5105.9 2060.54  5134.2 2065.15  5148.3 2065.53
#Mann=4,-1,0
  4325.4   0.035       0  4422.4    0.07       0  4999.0    0.05       0
  5009.7    0.07       0
Bank Sta=4999,5009.7
Exp/Cntr=0.3,0.1

Type RM Length L Ch R = 1,7409,483,483,483
BEGIN DESCRIPTION:
Stream0353 16.0
END DESCRIPTION:
XS GIS Cut Line= 4
      1834670.24     13985803.12      1834761.68     13985211.22
      1834705.11     13985106.95      1834414.10     13985031.81
#Sta/Elev= 30
  4347.0 2049.84  4547.5 2048.91  4567.7 2047.99  4628.4 2047.86  4668.4 2046.38
  4736.5 2046.12  4749.8 2045.23  4804.7 2044.69  4840.9 2042.73  4851.0 2043.04
  4945.9 2039.87  4992.1 2035.18  4998.5 2034.15  5002.9 2030.97  5003.4 2030.47
  5013.6 2030.97  5014.0 2031.89  5030.1 2032.62  5052.0 2042.37  5062.8 2045.84
  5106.0 2049.16  5132.1 2053.21  5157.6 2054.28  5176.8 2056.56  5239.6 2060.48
  5281.5 2063.65  5294.7 2063.02  5312.5 2064.23  5360.1 2064.52  5365.1 2064.45
#Mann=6,-1,0
  4347.0    0.07       0  5002.9    0.05       0  5013.6    0.07       0
  5176.8   0.035       0  5239.6    0.07       0  5360.1   0.035       0
Bank Sta=5002.9,5013.6
Exp/Cntr=0.3,0.1

Type RM Length L Ch R = 1,6926,470,470,470
BEGIN DESCRIPTION:
Stream0353 15.0
END DESCRIPTION:
XS GIS Cut Line= 3
      1835504.60     13985597.90      1835125.00     13984925.00
      1834975.01     13984775.01
#Sta/Elev= 30
  4227.4 2058.82  4391.5 2054.30  4552.2 2048.00  4581.8 2047.22  4587.6 2047.71
  4609.6 2046.31  4749.4 2043.47  4793.3 2041.34  4824.5 2041.03  4830.2 2039.78
  4862.1 2039.11  4867.8 2038.09  4882.3 2037.62  4911.1 2035.91  4932.8 2033.38
  4948.7 2032.73  4954.5 2030.96  4970.7 2028.64  4977.0 2027.61  4986.3 2028.06
  4988.8 2026.46  4989.3 2025.96  5005.4 2026.46  5013.7 2027.47  5035.3 2031.76
  5042.4 2036.82  5070.7 2043.46  5117.4 2049.85  5183.8 2056.34  5212.1 2057.63
#Mann=7,-1,0
  4227.4    0.07       0  4882.3   0.035       0  4970.7    0.07       0
  4988.8    0.05       0  5005.4    0.07       0  5013.7   0.035       0
  5117.4    0.07       0
Bank Sta=4988.8,5005.4
Exp/Cntr=0.3,0.1

Type RM Length L Ch R = 1,6456,437,437,437
BEGIN DESCRIPTION:
Stream0353 14.0
END DESCRIPTION:
XS GIS Cut Line= 3
      1836192.80     13984985.82      1835475.00     13984625.00
      1835325.01     13984475.01
#Sta/Elev= 30
  4196.3 2061.11  4388.5 2054.48  4522.5 2047.76  4695.5 2041.46  4820.6 2034.82
  4843.0 2034.64  4874.1 2032.06  4896.4 2029.18  4902.0 2027.87  4918.8 2027.92
  4924.3 2026.92  4941.1 2028.82  4954.9 2025.95  4963.4 2025.00  4969.0 2025.44
  4977.3 2024.28  4977.8 2023.78  4993.7 2023.78  4994.2 2024.28  4996.9 2026.01
  5003.2 2026.01  5013.8 2027.59  5028.0 2033.35  5042.1 2037.31  5070.4 2041.81
  5093.1 2044.50  5155.3 2049.87  5183.5 2052.99  5209.0 2054.64  5211.8 2054.64
#Mann=5,-1,0
  4196.3    0.07       0  4977.3    0.05       0  4994.2    0.07       0
  5093.1   0.035       0  5209.0    0.07       0
Bank Sta=4977.3,4994.2
Exp/Cntr=0.3,0.1

Type RM Length L Ch R = 1,6019,494,494,494
BEGIN DESCRIPTION:
Stream0353 13.0
END DESCRIPTION:
XS GIS Cut Line= 3
      1836025.00     13984675.00      1835825.00     13984475.00
      1835624.99     13983924.98
#Sta/Elev= 30
  4708.8 2046.48  4920.9 2036.12  4949.2 2032.78  4977.5 2025.95  4979.7 2024.42
  4980.2 2023.92  4996.6 2024.42  5006.9 2026.06  5093.4 2025.64  5118.7 2027.19
  5140.6 2031.87  5193.8 2034.58  5204.5 2034.54  5210.4 2033.06  5215.8 2035.40
  5235.7 2033.07  5241.0 2035.56  5251.6 2033.77  5266.3 2032.19  5271.6 2034.09
  5277.2 2033.60  5296.9 2035.65  5302.2 2034.57  5327.5 2040.51  5332.8 2039.74
  5352.8 2042.19  5411.5 2046.09  5517.3 2051.56  5561.6 2055.20  5576.9 2055.09
#Mann=7,-1,0
  4708.8    0.07       0  4979.7    0.05       0  4996.6    0.07       0
  5251.6   0.035       0  5277.2    0.07       0  5411.5   0.035       0
  5517.3    0.07       0
Bank Sta=4979.7,4996.6
Exp/Cntr=0.3,0.1

Type RM Length L Ch R = 1,5525,463,463,463
BEGIN DESCRIPTION:
Stream0353 12.0
END DESCRIPTION:
XS GIS Cut Line= 3
      1836224.99     13984324.96      1836175.00     13984125.00
      1835974.97     13983924.97
#Sta/Elev= 30
  4793.9 2041.47  4804.2 2041.41  4845.4 2039.14  4858.3 2038.74  4866.0 2037.51
  4886.6 2035.56  4894.4 2033.90  4899.5 2034.46  4907.2 2031.25  4935.6 2026.73
  4940.7 2024.41  4948.5 2022.41  4950.2 2020.87  4950.7 2020.37  4966.8 2020.37
  4967.3 2020.87  4997.4 2021.79  5014.2 2021.48  5028.3 2022.49  5042.4 2024.65
  5070.7 2026.14  5084.9 2027.66  5141.4 2029.60  5169.7 2032.67  5183.9 2033.51
  5212.1 2037.37  5226.3 2038.82  5247.5 2039.88  5254.6 2041.40  5282.9 2042.65
#Mann=3,-1,0
  4793.9   0.035       0  4950.2    0.05       0  4967.3    0.07       0
Bank Sta=4950.2,4967.3
Exp/Cntr=0.3,0.1

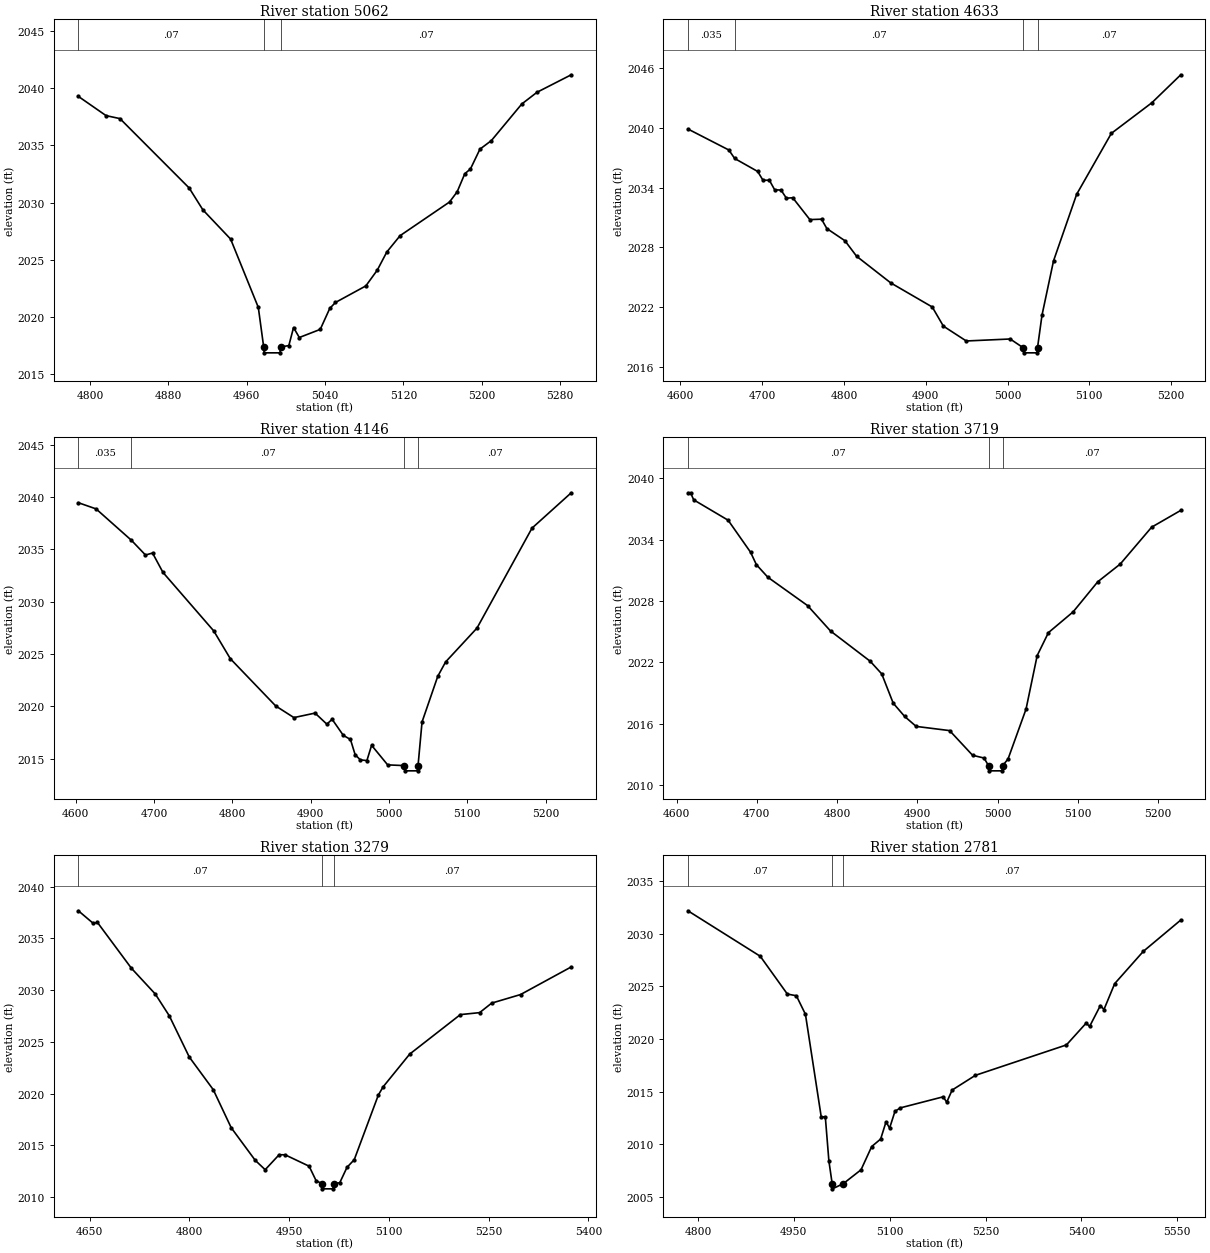
Type RM Length L Ch R = 1,5062,429,429,429
BEGIN DESCRIPTION:
Stream0353 11.0
END DESCRIPTION:
XS GIS Cut Line= 3
      1836575.03     13983925.03      1836425.00     13983775.00
      1836175.02     13983625.01
#Sta/Elev= 30
  4787.9 2039.28  4816.2 2037.60  4830.4 2037.34  4901.1 2031.28  4915.2 2029.36
  4943.5 2026.81  4971.8 2020.84  4977.3 2017.37  4977.8 2016.87  4994.0 2016.87
  4994.5 2017.37  5003.0 2017.51  5007.8 2019.08  5013.7 2018.21  5035.1 2018.92
  5044.8 2020.75  5050.6 2021.27  5081.7 2022.72  5093.4 2024.10  5103.1 2025.68
  5116.7 2027.11  5167.2 2030.05  5175.0 2030.94  5182.8 2032.52  5188.6 2032.94
  5198.3 2034.67  5210.0 2035.42  5241.1 2038.62  5256.6 2039.64  5291.6 2041.17
#Mann=3,-1,0
  4787.9    0.07       0  4977.3    0.05       0  4994.5    0.07       0
Bank Sta=4977.3,4994.5
Exp/Cntr=0.3,0.1

Type RM Length L Ch R = 1,4633,487,487,487
BEGIN DESCRIPTION:
Stream0353 10.0
END DESCRIPTION:
XS GIS Cut Line= 3
      1836825.02     13983725.02      1836575.00     13983425.00
      1836424.98     13983274.98
#Sta/Elev= 30
  4609.1 2039.88  4659.2 2037.77  4666.3 2036.92  4694.4 2035.62  4700.9 2034.74
  4708.7 2034.74  4715.2 2033.78  4723.0 2033.75  4729.5 2032.94  4737.3 2032.98
  4758.2 2030.79  4772.5 2030.83  4779.0 2029.89  4801.1 2028.67  4815.4 2027.11
  4857.1 2024.44  4907.9 2022.02  4921.5 2020.10  4949.5 2018.61  5003.2 2018.81
  5019.3 2017.92  5019.8 2017.42  5036.1 2017.42  5036.6 2017.92  5042.1 2021.20
  5056.2 2026.65  5084.5 2033.33  5126.9 2039.44  5176.4 2042.51  5211.8 2045.32
#Mann=4,-1,0
  4609.1   0.035       0  4666.3    0.07       0  5019.3    0.05       0
  5036.6    0.07       0
Bank Sta=5019.3,5036.6
Exp/Cntr=0.3,0.1

Type RM Length L Ch R = 1,4146,427,427,427
BEGIN DESCRIPTION:
Stream0353 9.0
END DESCRIPTION:
XS GIS Cut Line= 3
      1837125.00     13983425.00      1836904.03     13983091.97
      1836675.02     13983075.00
#Sta/Elev= 30
  4603.5 2039.47  4626.1 2038.88  4671.2 2035.88  4689.2 2034.47  4698.2 2034.66
  4711.5 2032.81  4776.4 2027.21  4797.5 2024.56  4855.5 2020.04  4878.7 2018.93
  4905.7 2019.36  4920.8 2018.30  4927.5 2018.77  4941.8 2017.23  4950.9 2016.84
  4956.9 2015.38  4963.5 2014.89  4971.9 2014.82  4977.9 2016.28  4998.4 2014.41
  5019.9 2014.34  5020.4 2013.84  5036.7 2013.84  5037.2 2014.34  5042.3 2018.51
  5062.4 2022.88  5072.4 2024.25  5112.5 2027.49  5182.7 2037.04  5232.8 2040.42
#Mann=4,-1,0
  4603.5   0.035       0  4671.2    0.07       0  5019.9    0.05       0
  5037.2    0.07       0
Bank Sta=5019.9,5037.2
Exp/Cntr=0.3,0.1

Type RM Length L Ch R = 1,3719,440,440,440
BEGIN DESCRIPTION:
Stream0353 8.0
END DESCRIPTION:
XS GIS Cut Line= 3
      1837475.00     13983125.00      1837225.00     13982825.00
      1837025.02     13982725.01
#Sta/Elev= 30
  4614.1 2038.57  4617.4 2038.57  4621.3 2037.88  4664.2 2035.89  4692.2 2032.76
  4699.4 2031.55  4713.7 2030.32  4763.2 2027.55  4791.8 2025.07  4841.3 2022.11
  4855.6 2020.88  4869.9 2018.02  4884.2 2016.72  4898.5 2015.75  4940.2 2015.34
  4968.8 2012.93  4983.1 2012.66  4988.7 2011.91  4989.2 2011.41  5005.7 2011.41
  5006.2 2011.91  5013.0 2012.57  5035.4 2017.44  5049.3 2022.67  5063.3 2024.91
  5094.1 2026.94  5124.8 2029.88  5152.8 2031.61  5191.9 2035.21  5228.2 2036.85
#Mann=3,-1,0
  4614.1    0.07       0  4988.7    0.05       0  5006.2    0.07       0
Bank Sta=4988.7,5006.2
Exp/Cntr=0.3,0.1

Type RM Length L Ch R = 1,3279,498,498,498
BEGIN DESCRIPTION:
Stream0353 7.0
END DESCRIPTION:
XS GIS Cut Line= 3
      1837875.04     13982775.03      1837575.00     13982575.00
      1837224.99     13982425.00
#Sta/Elev= 30
  4632.9 2037.68  4655.5 2036.45  4661.5 2036.56  4712.6 2032.13  4748.6 2029.63
  4769.7 2027.52  4799.7 2023.54  4835.8 2020.38  4862.8 2016.70  4898.9 2013.55
  4913.9 2012.64  4934.9 2014.09  4943.9 2014.08  4980.0 2012.98  4990.5 2011.58
  4999.3 2011.29  4999.8 2010.79  5016.3 2010.79  5016.8 2011.29  5026.1 2011.38
  5037.0 2012.87  5047.9 2013.61  5084.2 2019.87  5091.4 2020.66  5131.3 2023.82
  5207.5 2027.64  5236.5 2027.83  5254.6 2028.75  5298.1 2029.58  5374.3 2032.25
#Mann=3,-1,0
  4632.9    0.07       0  4999.3    0.05       0  5016.8    0.07       0
Bank Sta=4999.3,5016.8
Exp/Cntr=0.3,0.1

Type RM Length L Ch R = 1,2781,431,431,431
BEGIN DESCRIPTION:
Stream0353 6.0
END DESCRIPTION:
XS GIS Cut Line= 3
      1838075.03     13982375.03      1837925.00     13982225.00
      1837424.99     13981975.00
#Sta/Elev= 30
  4784.3 2032.18  4897.5 2027.86  4939.9 2024.27  4954.0 2024.11  4968.2 2022.35
  4992.9 2012.61  4999.3 2012.61  5004.9 2008.42  5010.0 2006.27  5010.5 2005.77
  5027.6 2006.27  5055.2 2007.58  5071.9 2009.79  5085.9 2010.50  5094.3 2012.13
  5099.9 2011.54  5108.3 2013.13  5116.7 2013.46  5183.7 2014.51  5189.3 2014.00
  5197.7 2015.15  5234.1 2016.55  5376.6 2019.44  5407.3 2021.50  5412.9 2021.20
  5429.7 2023.18  5435.3 2022.80  5452.1 2025.26  5496.8 2028.32  5555.5 2031.30
#Mann=3,-1,0
  4784.3    0.07       0  5010.0    0.05       0  5027.6    0.07       0
Bank Sta=5010,5027.6
Exp/Cntr=0.3,0.1

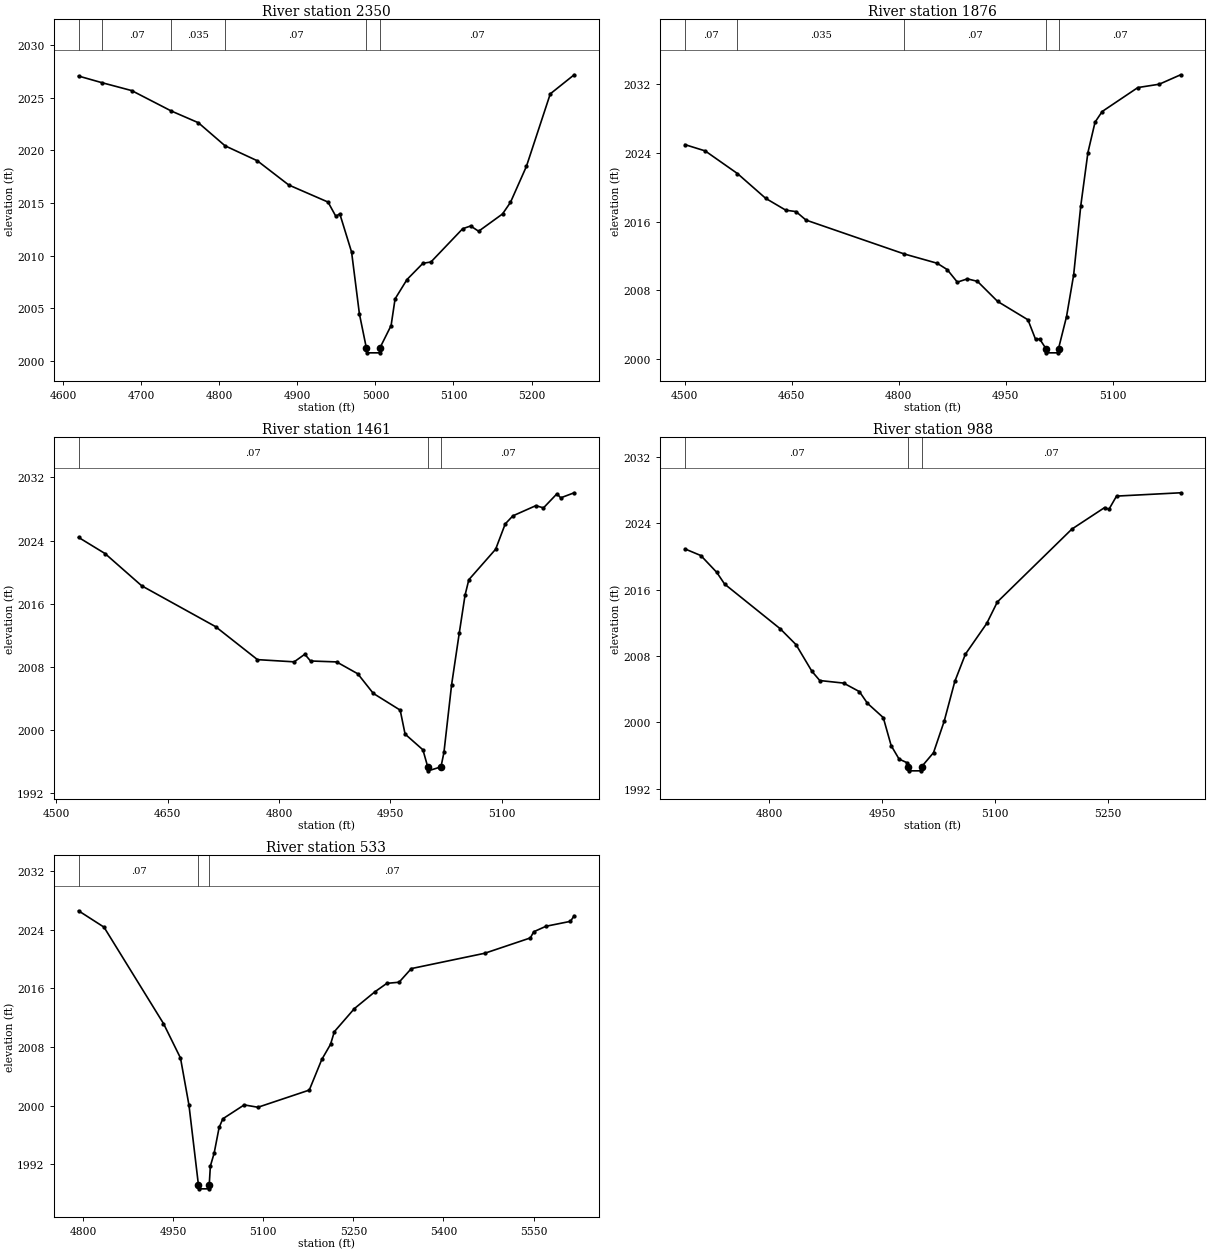
Type RM Length L Ch R = 1,2350,474,474,474
BEGIN DESCRIPTION:
Stream0353 5.0
END DESCRIPTION:
XS GIS Cut Line= 3
      1838202.65     13981866.93      1837825.00     13981825.00
      1837575.02     13981775.00
#Sta/Elev= 30
  4619.7 2027.04  4649.2 2026.42  4687.8 2025.66  4738.6 2023.72  4773.2 2022.61
  4807.4 2020.42  4848.7 2019.00  4889.0 2016.70  4939.3 2015.08  4949.3 2013.73
  4954.4 2013.96  4969.5 2010.33  4979.5 2004.47  4988.3 2001.27  4988.8 2000.77
  5005.5 2000.77  5006.0 2001.27  5020.1 2003.36  5025.2 2005.89  5040.5 2007.73
  5060.9 2009.27  5071.1 2009.39  5111.8 2012.55  5122.0 2012.81  5132.2 2012.31
  5162.8 2013.95  5173.0 2015.05  5193.4 2018.46  5224.0 2025.35  5254.6 2027.16
#Mann=6,-1,0
  4619.7     0.1       0  4649.2    0.07       0  4738.6   0.035       0
  4807.4    0.07       0  4988.3    0.05       0  5006.0    0.07       0
Bank Sta=4988.3,5006
Exp/Cntr=0.3,0.1

Type RM Length L Ch R = 1,1876,415,415,415
BEGIN DESCRIPTION:
Stream0353 4.0
END DESCRIPTION:
XS GIS Cut Line= 3
      1838175.02     13981775.02      1837825.00     13981425.00
      1837625.00     13981425.00
#Sta/Elev= 30
  4500.2 2024.97  4528.5 2024.24  4573.8 2021.60  4613.4 2018.71  4641.6 2017.33
  4655.8 2017.17  4669.9 2016.18  4807.7 2012.23  4853.8 2011.15  4867.9 2010.41
  4882.1 2008.95  4896.2 2009.33  4910.3 2009.04  4938.6 2006.70  4981.1 2004.56
  4991.7 2002.30  4997.7 2002.30  5006.3 2001.21  5006.8 2000.71  5023.5 2000.71
  5024.0 2001.21  5035.2 2004.93  5045.2 2009.79  5055.2 2017.86  5065.2 2024.05
  5075.2 2027.59  5085.2 2028.83  5135.2 2031.62  5165.2 2032.01  5195.2 2033.11
#Mann=5,-1,0
  4500.2    0.07       0  4573.8   0.035       0  4807.7    0.07       0
  5006.3    0.05       0  5024.0    0.07       0
Bank Sta=5006.3,5024
Exp/Cntr=0.3,0.1

Type RM Length L Ch R = 1,1461,473,473,473
BEGIN DESCRIPTION:
Stream0353 3.0
END DESCRIPTION:
XS GIS Cut Line= 3
      1838475.02     13981475.01      1838125.00     13981175.00
      1837924.96     13981124.99
#Sta/Elev= 30
  4530.1 2024.40  4565.8 2022.35  4615.2 2018.27  4714.5 2013.11  4771.0 2008.93
  4820.4 2008.65  4834.7 2009.61  4842.4 2008.76  4877.5 2008.64  4906.0 2007.14
  4926.9 2004.66  4963.1 2002.54  4969.7 1999.51  4993.7 1997.52  5000.2 1995.36
  5000.7 1994.86  5018.0 1995.36  5022.0 1997.19  5032.3 2005.74  5042.6 2012.27
  5050.4 2017.08  5055.5 2019.04  5091.6 2022.90  5104.5 2026.10  5114.8 2027.12
  5145.7 2028.41  5156.0 2028.13  5174.1 2029.91  5179.2 2029.40  5197.3 2030.04
#Mann=3,-1,0
  4530.1    0.07       0  5000.2    0.05       0  5018.0    0.07       0
Bank Sta=5000.2,5018
Exp/Cntr=0.3,0.1

Type RM Length L Ch R = 1,988,455,455,455
BEGIN DESCRIPTION:
Stream0353 2.0
END DESCRIPTION:
XS GIS Cut Line= 4
      1838625.01     13981275.04      1838525.00     13980975.00
      1838375.00     13980825.00      1838261.82     13980760.05
#Sta/Elev= 30
  4687.9 2020.93  4709.0 2020.13  4730.1 2018.11  4740.6 2016.69  4814.4 2011.31
  4835.5 2009.39  4856.6 2006.18  4867.1 2005.06  4898.8 2004.75  4919.8 2003.72
  4930.4 2002.32  4951.5 2000.59  4962.0 1997.21  4972.5 1995.59  4983.1 1995.15
  4984.7 1994.67  4985.2 1994.17  5002.0 1994.17  5002.5 1994.67  5018.3 1996.36
  5032.5 2000.16  5046.6 2004.95  5060.7 2008.24  5089.0 2011.94  5103.2 2014.54
  5202.2 2023.32  5245.8 2025.92  5251.5 2025.71  5261.6 2027.30  5346.8 2027.70
#Mann=3,-1,0
  4687.9    0.07       0  4984.7    0.05       0  5002.5    0.07       0
Bank Sta=4984.7,5002.5
Exp/Cntr=0.3,0.1

Type RM Length L Ch R = 1,533,0,0,0
BEGIN DESCRIPTION:
Stream0353 1.0
END DESCRIPTION:
XS GIS Cut Line= 4
      1839074.99     13980974.99      1838925.00     13980825.00
      1838725.00     13980675.00      1838368.94     13980606.02
#Sta/Elev= 30
  4792.7 2026.57  4835.1 2024.34  4934.1 2011.20  4962.4 2006.50  4976.5 2000.08
  4992.3 1989.17  4992.8 1988.67  5009.7 1988.67  5010.2 1989.17  5012.1 1991.77
  5018.4 1993.53  5026.7 1997.04  5032.9 1998.22  5068.4 2000.11  5091.3 1999.79
  5176.7 2002.13  5197.5 2006.30  5212.1 2008.37  5218.4 2010.09  5251.7 2013.23
  5285.8 2015.52  5305.8 2016.68  5326.1 2016.83  5346.5 2018.69  5468.7 2020.78
  5544.6 2022.87  5550.2 2023.71  5570.6 2024.46  5611.3 2025.13  5617.5 2025.89
#Mann=3,-1,0
  4792.7    0.07       0  4992.3    0.05       0  5010.2    0.07       0
Bank Sta=4992.3,5010.2
Exp/Cntr=0.3,0.1

Chan Stop Cuts=-1