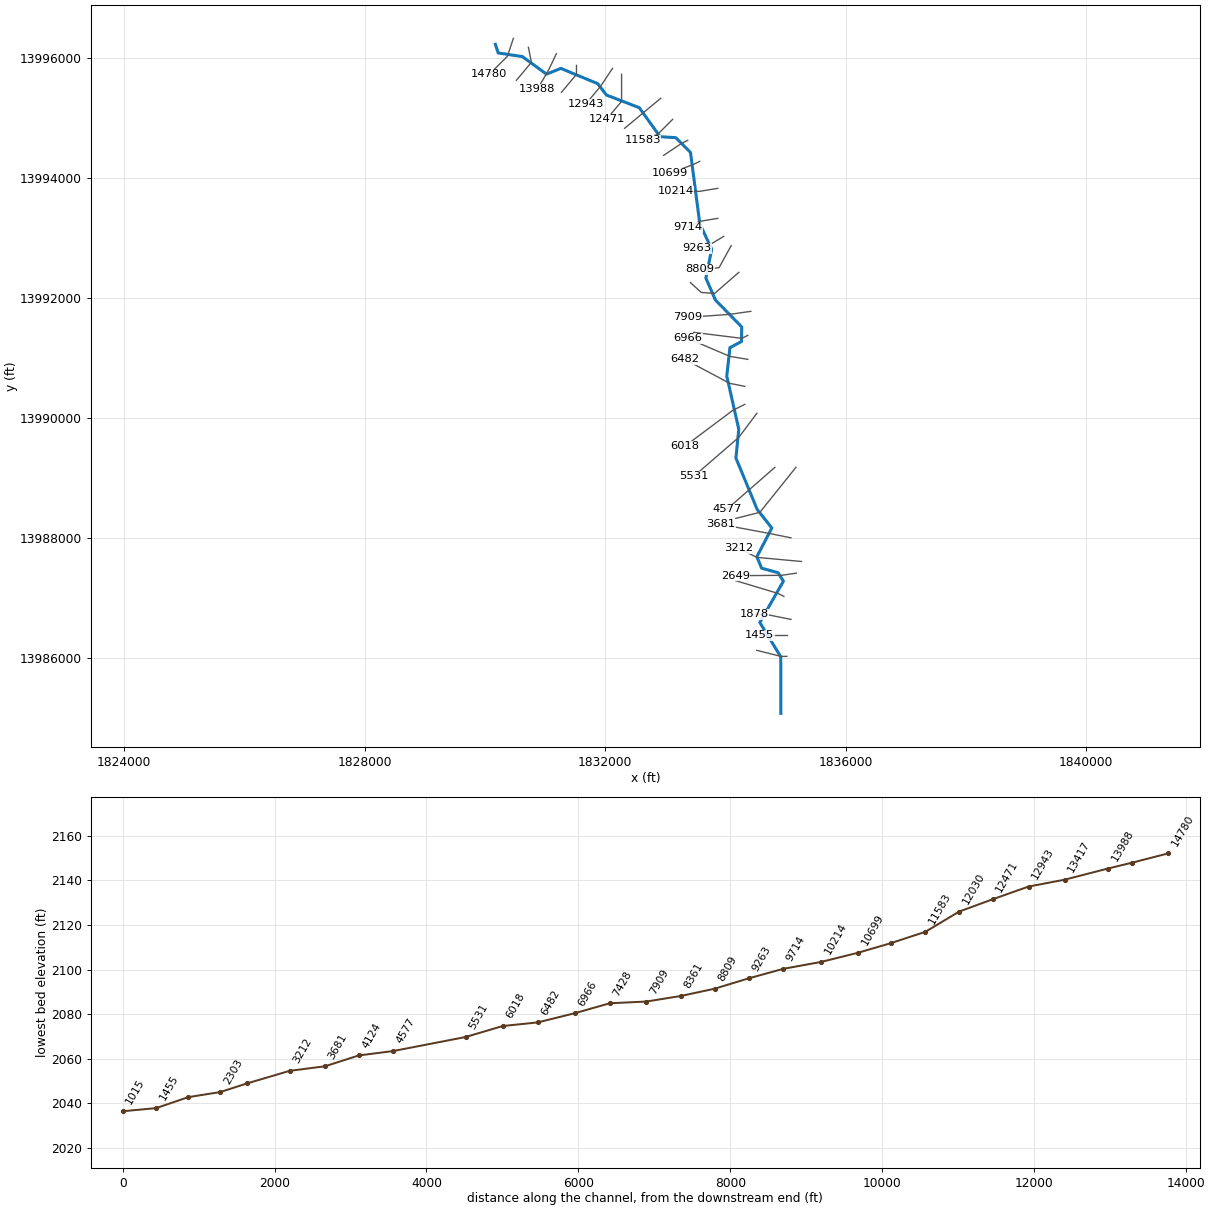
--- Stream0358.prj (project) ---

Proj Title=Stream0358 Base Level Engineering
Current Plan=p01
Default Exp/Contr=0.3,0.1
English Units
Geom File=g01
Flow File=f01
Plan File=p01
BEGIN DESCRIPTION:
Stream0358
END DESCRIPTION:

--- Stream0358.p01 (plan) ---

Plan Title=Multiple Run
Short Identifier=Multiple
Geom File=g01
Flow File=f01
Subcritical Flow
K Sum by GR= 0
Std Step Tol= 0.01
Critical Tol= 0.01
Num of Std Step Trials= 20
Max Error Tol= 0.3
Flow Tol Ratio= 0.001
Split Flow NTrial= 30
Split Flow Tol= 0.02
Split Flow Ratio= 0.02
Log Output Level= 0
Friction Slope Method= 1
Unsteady Friction Slope Method= 2
Unsteady Bridges Friction Slope Method= 1
Parabolic Critical Depth
Global Vel Dist=  1 , 1 , 1
Global Log Level= 0
CheckData=True
Encroach Param= -1, 0, 0, 0
BEGIN DESCRIPTION:
Multiple Run
END DESCRIPTION:

--- Stream0358.f01 (steady flow) ---

Flow Title=Multiple
Number of Profiles=7
Profile Names=10-year,25-year,50-year,1pct_min,100-year,1pct_plu,500-year
River Rch & RM= Stream0358,Reach-1,14780
     848    1415    1942    1287    2569    5125    4442
River Rch & RM= Stream0358,Reach-1,11583
    1243    2125    2961    1992    3974    7929    7077
River Rch & RM= Stream0358,Reach-1,10214
    1822    3180    4495    3062    6110   12192   11171
River Rch & RM= Stream0358,Reach-1,8809
    2300    4047    5752    3935    7852   15667   14483
Boundary for River Rch & Prof#=Stream0358,Reach-1,1
Up Type=0
Dn Type=3
Dn Slope=0.005
Boundary for River Rch & Prof#=Stream0358,Reach-1,2
Up Type=0
Dn Type=3
Dn Slope=0.005
Boundary for River Rch & Prof#=Stream0358,Reach-1,3
Up Type=0
Dn Type=3
Dn Slope=0.005
Boundary for River Rch & Prof#=Stream0358,Reach-1,4
Up Type=0
Dn Type=3
Dn Slope=0.005
Boundary for River Rch & Prof#=Stream0358,Reach-1,5
Up Type=0
Dn Type=3
Dn Slope=0.005
Boundary for River Rch & Prof#=Stream0358,Reach-1,6
Up Type=0
Dn Type=3
Dn Slope=0.005
Boundary for River Rch & Prof#=Stream0358,Reach-1,7
Up Type=0
Dn Type=3
Dn Slope=0.005

--- Stream0358.g01 (geometry) ---

Geom Title=Existing Conditions

River Reach=Stream0358,Reach-1
Reach XY= 30
      1830175.00     13996225.00      1830222.67     13996080.83
      1830623.28     13996021.66      1831026.65     13995728.10
      1831264.45     13995823.90      1831877.44     13995569.48
      1832022.33     13995380.42      1832569.39     13995169.41
      1832915.20     13994685.47      1833177.45     13994669.54
      1833421.39     13994423.50      1833576.06     13993235.44
      1833774.48     13992809.78      1833677.23     13992330.93
      1833835.11     13991965.05      1834273.95     13991514.57
      1834269.54     13991272.52      1834077.06     13991169.54
      1834025.06     13990695.03      1834224.61     13989809.84
      1834176.80     13989331.11      1834530.84     13988472.71
      1834774.41     13988164.38      1834525.76     13987685.69
      1834604.36     13987494.43      1834877.68     13987419.58
      1834966.96     13987278.32      1834574.23     13986590.09
      1834922.76     13986019.07      1834925.00     13985075.00

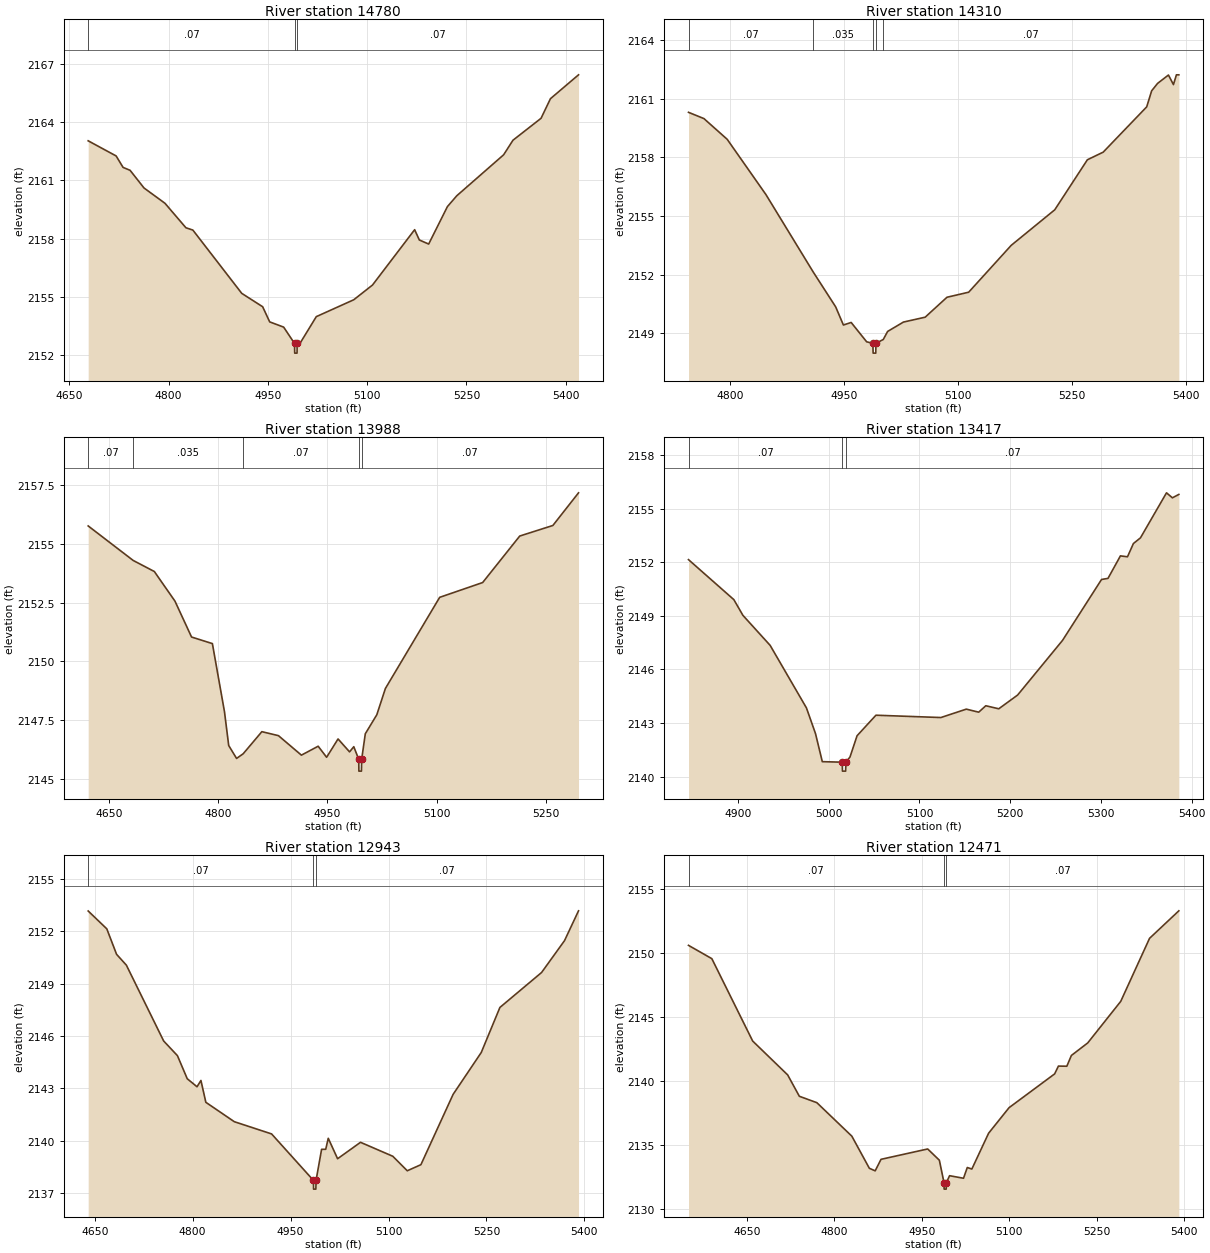
Type RM Length L Ch R = 1,14780,470,470,470
BEGIN DESCRIPTION:
Stream0358 31.0
END DESCRIPTION:
XS GIS Cut Line= 3
      1830475.01     13996325.02      1830375.00     13996025.00
      1830075.01     13995725.01
#Sta/Elev= 30
  4678.7 2163.04  4720.9 2162.26  4731.4 2161.67  4742.0 2161.52  4763.0 2160.61
  4794.7 2159.82  4826.3 2158.56  4836.8 2158.44  4910.6 2155.18  4942.2 2154.49
  4952.8 2153.71  4973.9 2153.44  4990.3 2152.60  4990.6 2152.10  4994.1 2152.10
  4994.3 2152.60  4998.5 2152.60  5023.2 2153.98  5079.8 2154.85  5108.1 2155.61
  5171.7 2158.46  5178.8 2157.93  5192.9 2157.72  5221.2 2159.65  5235.4 2160.21
  5306.1 2162.32  5320.2 2163.07  5362.6 2164.20  5376.8 2165.21  5419.2 2166.44
#Mann=3,-1,0
  4678.7    0.07       0  4990.3    0.05       0  4994.3    0.07       0
Bank Sta=4990.3,4994.3
Exp/Cntr=0.3,0.1

Type RM Length L Ch R = 1,14310,322,322,322
BEGIN DESCRIPTION:
Stream0358 30.0
END DESCRIPTION:
XS GIS Cut Line= 3
      1830725.01     13996174.95      1830775.00     13995925.00
      1830525.01     13995625.01
#Sta/Elev= 30
  4745.1 2160.31  4765.4 2159.99  4796.0 2158.93  4847.0 2156.10  4909.0 2152.15
  4938.8 2150.35  4949.0 2149.42  4959.2 2149.55  4979.6 2148.56  4987.8 2148.48
  4988.1 2147.98  4991.6 2147.98  4991.8 2148.48  5001.5 2148.68  5007.2 2149.09
  5028.0 2149.57  5056.6 2149.82  5085.3 2150.84  5113.9 2151.10  5169.9 2153.50
  5227.2 2155.32  5270.1 2157.88  5290.9 2158.27  5348.2 2160.59  5354.7 2161.41
  5362.5 2161.79  5376.8 2162.22  5383.4 2161.73  5387.3 2162.23  5390.5 2162.23
#Mann=5,-1,0
  4745.1    0.07       0  4909.0   0.035       0  4987.8   0.035       0
  4991.8   0.035       0  5001.5    0.07       0
Bank Sta=4987.8,4991.8
Exp/Cntr=0.3,0.1

Type RM Length L Ch R = 1,13988,571,571,571
BEGIN DESCRIPTION:
Stream0358 29.0
END DESCRIPTION:
XS GIS Cut Line= 3
      1831190.27     13996069.13      1831070.18     13995815.30
      1830875.00     13995475.00
#Sta/Elev= 30
  4621.7 2155.76  4683.5 2154.29  4712.5 2153.82  4740.8 2152.56  4763.6 2151.03
  4792.2 2150.75  4808.8 2147.85  4814.6 2146.41  4825.4 2145.86  4834.5 2146.06
  4860.1 2147.00  4882.9 2146.83  4914.4 2146.00  4937.4 2146.38  4949.0 2145.91
  4964.7 2146.69  4980.5 2146.14  4986.3 2146.36  4993.1 2145.82  4993.3 2145.32
  4996.8 2145.32  4997.1 2145.82  5002.1 2146.91  5017.9 2147.72  5029.7 2148.84
  5104.2 2152.72  5163.2 2153.35  5214.1 2155.33  5259.6 2155.78  5294.8 2157.17
#Mann=5,-1,0
  4621.7    0.07       0  4683.5   0.035       0  4834.5    0.07       0
  4993.1    0.05       0  4997.1    0.07       0
Bank Sta=4993.1,4997.1
Exp/Cntr=0.3,0.1

Type RM Length L Ch R = 1,13417,474,474,474
BEGIN DESCRIPTION:
Stream0358 28.0
END DESCRIPTION:
XS GIS Cut Line= 3
      1831525.00     13995875.01      1831525.00     13995725.00
      1831275.01     13995425.02
#Sta/Elev= 30
  4845.4 2152.15  4895.4 2149.91  4905.4 2149.03  4935.4 2147.35  4975.4 2143.85
  4985.4 2142.41  4992.9 2140.84  5014.9 2140.81  5015.1 2140.31  5018.6 2140.31
  5018.9 2140.81  5023.4 2141.10  5031.2 2142.29  5052.0 2143.44  5123.6 2143.31
  5151.6 2143.78  5165.3 2143.61  5173.1 2143.97  5187.4 2143.80  5208.2 2144.57
  5257.7 2147.63  5300.7 2151.04  5307.8 2151.10  5321.5 2152.36  5329.3 2152.31
  5335.8 2153.05  5343.6 2153.37  5372.3 2155.89  5378.8 2155.61  5385.9 2155.80
#Mann=3,-1,0
  4845.4    0.07       0  5014.9    0.05       0  5018.9    0.07       0
Bank Sta=5014.9,5018.9
Exp/Cntr=0.3,0.1

Type RM Length L Ch R = 1,12943,472,472,472
BEGIN DESCRIPTION:
Stream0358 27.0
END DESCRIPTION:
XS GIS Cut Line= 3
      1832124.97     13995824.96      1831925.00     13995525.00
      1831675.01     13995225.02
#Sta/Elev= 30
  4640.0 2153.16  4668.5 2152.14  4683.5 2150.68  4698.5 2150.06  4755.6 2145.72
  4776.7 2144.88  4791.7 2143.56  4806.7 2143.10  4812.7 2143.46  4820.2 2142.21
  4863.8 2141.10  4920.9 2140.40  4985.0 2137.74  4985.2 2137.24  4988.7 2137.24
  4989.0 2137.74  4997.5 2139.52  5003.8 2139.52  5007.7 2140.15  5022.0 2138.98
  5057.1 2139.92  5106.6 2139.12  5128.7 2138.29  5149.6 2138.64  5199.0 2142.67
  5242.0 2145.06  5270.6 2147.64  5334.4 2149.64  5369.5 2151.46  5391.0 2153.17
#Mann=3,-1,0
  4640.0    0.07       0  4985.0    0.05       0  4989.0    0.07       0
Bank Sta=4985,4989
Exp/Cntr=0.3,0.1

Type RM Length L Ch R = 1,12471,441,441,441
BEGIN DESCRIPTION:
Stream0358 26.0
END DESCRIPTION:
XS GIS Cut Line= 3
      1832275.00     13995724.95      1832275.00     13995275.00
      1832024.98     13994974.97
#Sta/Elev= 30
  4550.0 2150.60  4590.0 2149.56  4660.0 2143.12  4720.0 2140.47  4740.0 2138.80
  4770.0 2138.30  4830.0 2135.68  4860.0 2133.17  4870.0 2132.97  4880.0 2133.87
  4960.0 2134.68  4980.0 2133.80  4988.0 2132.04  4988.2 2131.54  4991.7 2131.54
  4992.0 2132.04  4997.5 2132.59  5021.4 2132.39  5027.9 2133.23  5035.7 2133.11
  5064.4 2135.91  5099.5 2137.91  5177.6 2140.55  5184.1 2141.16  5198.5 2141.15
  5206.3 2141.99  5234.3 2142.97  5290.9 2146.22  5340.3 2151.15  5390.5 2153.30
#Mann=3,-1,0
  4550.0    0.07       0  4988.0    0.05       0  4992.0    0.07       0
Bank Sta=4988,4992
Exp/Cntr=0.3,0.1

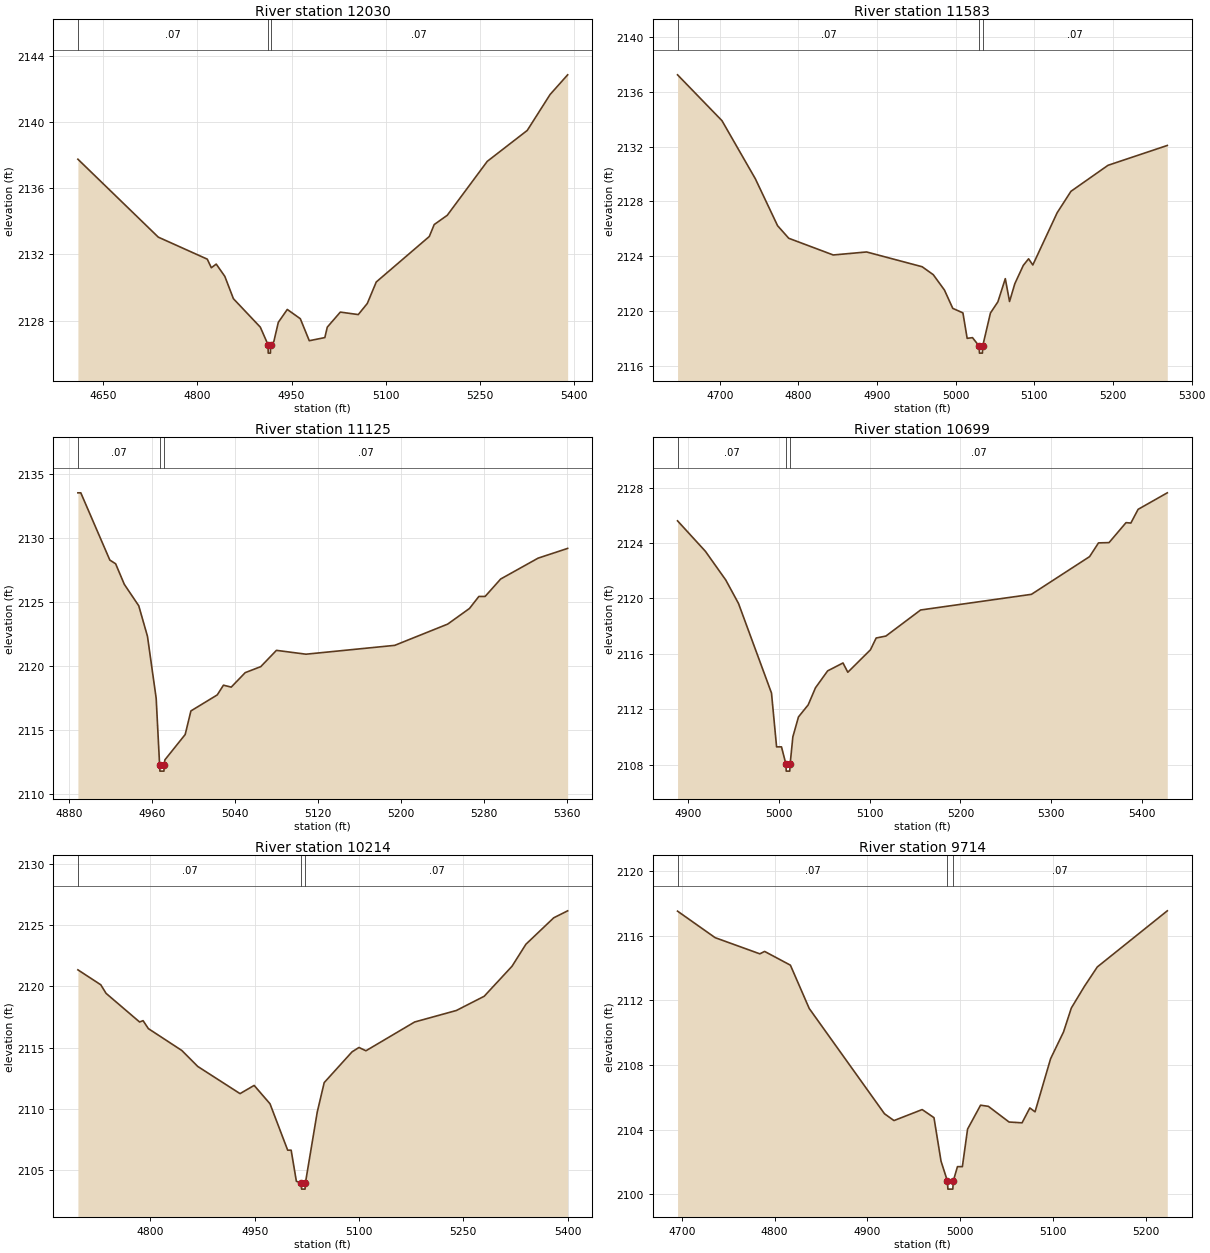
Type RM Length L Ch R = 1,12030,447,447,447
BEGIN DESCRIPTION:
Stream0358 25.0
END DESCRIPTION:
XS GIS Cut Line= 3
      1832925.00     13995325.00      1832625.00     13995075.00
      1832325.02     13994825.02
#Sta/Elev= 30
  4609.3 2137.75  4737.5 2133.04  4815.6 2131.71  4822.1 2131.19  4829.9 2131.41
  4843.6 2130.67  4857.3 2129.32  4900.2 2127.60  4912.6 2126.53  4912.8 2126.03
  4916.3 2126.03  4916.6 2126.53  4921.7 2126.72  4928.9 2127.89  4943.2 2128.67
  4964.0 2128.11  4978.3 2126.78  5003.1 2126.97  5007.0 2127.60  5027.8 2128.51
  5056.4 2128.36  5070.8 2129.03  5085.1 2130.33  5169.7 2133.08  5177.5 2133.80
  5198.3 2134.36  5262.1 2137.62  5325.9 2139.49  5362.3 2141.66  5390.3 2142.85
#Mann=3,-1,0
  4609.3    0.07       0  4912.6    0.05       0  4916.6    0.07       0
Bank Sta=4912.6,4916.6
Exp/Cntr=0.3,0.1

Type RM Length L Ch R = 1,11583,458,458,458
BEGIN DESCRIPTION:
Stream0358 24.0
END DESCRIPTION:
XS GIS Cut Line= 3
      1833124.98     13994974.98      1832875.00     13994725.00
      1832624.98     13994624.99
#Sta/Elev= 30
  4646.2 2137.25  4702.7 2133.90  4745.2 2129.65  4773.4 2126.23  4787.6 2125.31
  4844.2 2124.09  4886.6 2124.31  4957.3 2123.23  4971.4 2122.65  4985.6 2121.53
  4996.2 2120.19  5009.1 2119.86  5014.5 2118.00  5021.3 2118.05  5029.9 2117.42
  5030.1 2116.92  5033.9 2116.92  5034.2 2117.42  5044.1 2119.85  5053.6 2120.67
  5063.0 2122.36  5068.4 2120.69  5075.1 2121.99  5085.9 2123.33  5092.6 2123.81
  5098.0 2123.36  5129.0 2127.18  5146.5 2128.74  5193.6 2130.64  5269.0 2132.09
#Mann=3,-1,0
  4646.2    0.07       0  5029.9    0.05       0  5034.2    0.07       0
Bank Sta=5029.9,5034.2
Exp/Cntr=0.3,0.1

Type RM Length L Ch R = 1,11125,426,426,426
BEGIN DESCRIPTION:
Stream0358 23.0
END DESCRIPTION:
XS GIS Cut Line= 3
      1833375.03     13994625.02      1833275.00     13994575.00
      1832975.00     13994375.00
#Sta/Elev= 30
  4888.2 2133.53  4891.0 2133.53  4919.0 2128.28  4924.6 2127.99  4933.0 2126.38
  4946.9 2124.71  4955.3 2122.33  4963.7 2117.49  4967.0 2112.30  4967.3 2111.80
  4971.2 2111.80  4971.5 2112.30  4972.1 2112.68  4991.7 2114.66  4997.2 2116.50
  5022.6 2117.75  5028.6 2118.51  5036.1 2118.36  5049.6 2119.49  5064.6 2119.96
  5079.7 2121.23  5108.2 2120.93  5193.8 2121.62  5244.9 2123.28  5265.9 2124.50
  5275.0 2125.44  5281.0 2125.44  5296.0 2126.80  5332.1 2128.43  5360.6 2129.19
#Mann=3,-1,0
  4888.2    0.07       0  4967.0    0.05       0  4971.5    0.07       0
Bank Sta=4967,4971.5
Exp/Cntr=0.3,0.1

Type RM Length L Ch R = 1,10699,485,485,485
BEGIN DESCRIPTION:
Stream0358 22.0
END DESCRIPTION:
XS GIS Cut Line= 3
      1833574.97     13994274.99      1833475.00     13994225.00
      1833074.97     13994074.99
#Sta/Elev= 30
  4888.6 2125.60  4919.3 2123.40  4941.7 2121.33  4955.7 2119.64  4992.0 2113.18
  4997.6 2109.30  5003.0 2109.30  5007.9 2108.05  5008.2 2107.55  5012.1 2107.55
  5012.5 2108.05  5015.5 2110.02  5021.7 2111.46  5032.4 2112.33  5040.4 2113.56
  5053.8 2114.78  5070.7 2115.35  5076.0 2114.68  5100.9 2116.30  5107.2 2117.15
  5117.9 2117.29  5156.1 2119.17  5278.1 2120.30  5342.1 2123.02  5351.9 2124.01
  5363.5 2124.03  5382.2 2125.47  5387.5 2125.44  5395.5 2126.43  5427.6 2127.62
#Mann=3,-1,0
  4888.6    0.07       0  5007.9    0.05       0  5012.5    0.07       0
Bank Sta=5007.9,5012.5
Exp/Cntr=0.3,0.1

Type RM Length L Ch R = 1,10214,500,500,500
BEGIN DESCRIPTION:
Stream0358 21.0
END DESCRIPTION:
XS GIS Cut Line= 3
      1833874.96     13993824.99      1833575.00     13993775.00
      1833175.00     13993775.00
#Sta/Elev= 30
  4695.9 2121.35  4728.8 2120.13  4736.4 2119.43  4784.6 2117.09  4789.6 2117.20
  4797.2 2116.55  4845.4 2114.76  4868.2 2113.46  4929.0 2111.24  4949.3 2111.91
  4972.1 2110.41  4997.5 2106.62  5002.5 2106.62  5010.0 2104.08  5017.0 2103.94
  5017.5 2103.44  5022.5 2103.44  5023.0 2103.94  5040.0 2109.73  5050.0 2112.14
  5090.0 2114.65  5100.0 2115.01  5110.0 2114.74  5180.0 2117.09  5240.0 2118.03
  5280.0 2119.19  5320.0 2121.64  5340.0 2123.44  5380.0 2125.60  5400.0 2126.17
#Mann=3,-1,0
  4695.9    0.07       0  5017.0    0.05       0  5023.0    0.07       0
Bank Sta=5017,5023
Exp/Cntr=0.3,0.1

Type RM Length L Ch R = 1,9714,451,451,451
BEGIN DESCRIPTION:
Stream0358 20.0
END DESCRIPTION:
XS GIS Cut Line= 3
      1833874.99     13993325.00      1833575.00     13993275.00
      1833375.03     13993175.02
#Sta/Elev= 30
  4695.4 2117.51  4735.9 2115.87  4784.1 2114.87  4789.2 2115.02  4817.0 2114.17
  4837.3 2111.49  4918.4 2104.98  4928.6 2104.56  4959.0 2105.24  4971.7 2104.74
  4979.3 2102.05  4986.2 2100.82  4986.7 2100.32  4992.0 2100.32  4992.5 2100.82
  4997.0 2101.71  5002.3 2101.71  5007.9 2104.03  5021.9 2105.51  5030.3 2105.44
  5052.6 2104.47  5066.6 2104.42  5075.0 2105.34  5080.6 2105.10  5097.4 2108.39
  5111.3 2110.04  5119.7 2111.52  5133.7 2112.85  5147.7 2114.06  5223.1 2117.53
#Mann=3,-1,0
  4695.4    0.07       0  4986.2    0.05       0  4992.5    0.07       0
Bank Sta=4986.2,4992.5
Exp/Cntr=0.3,0.1

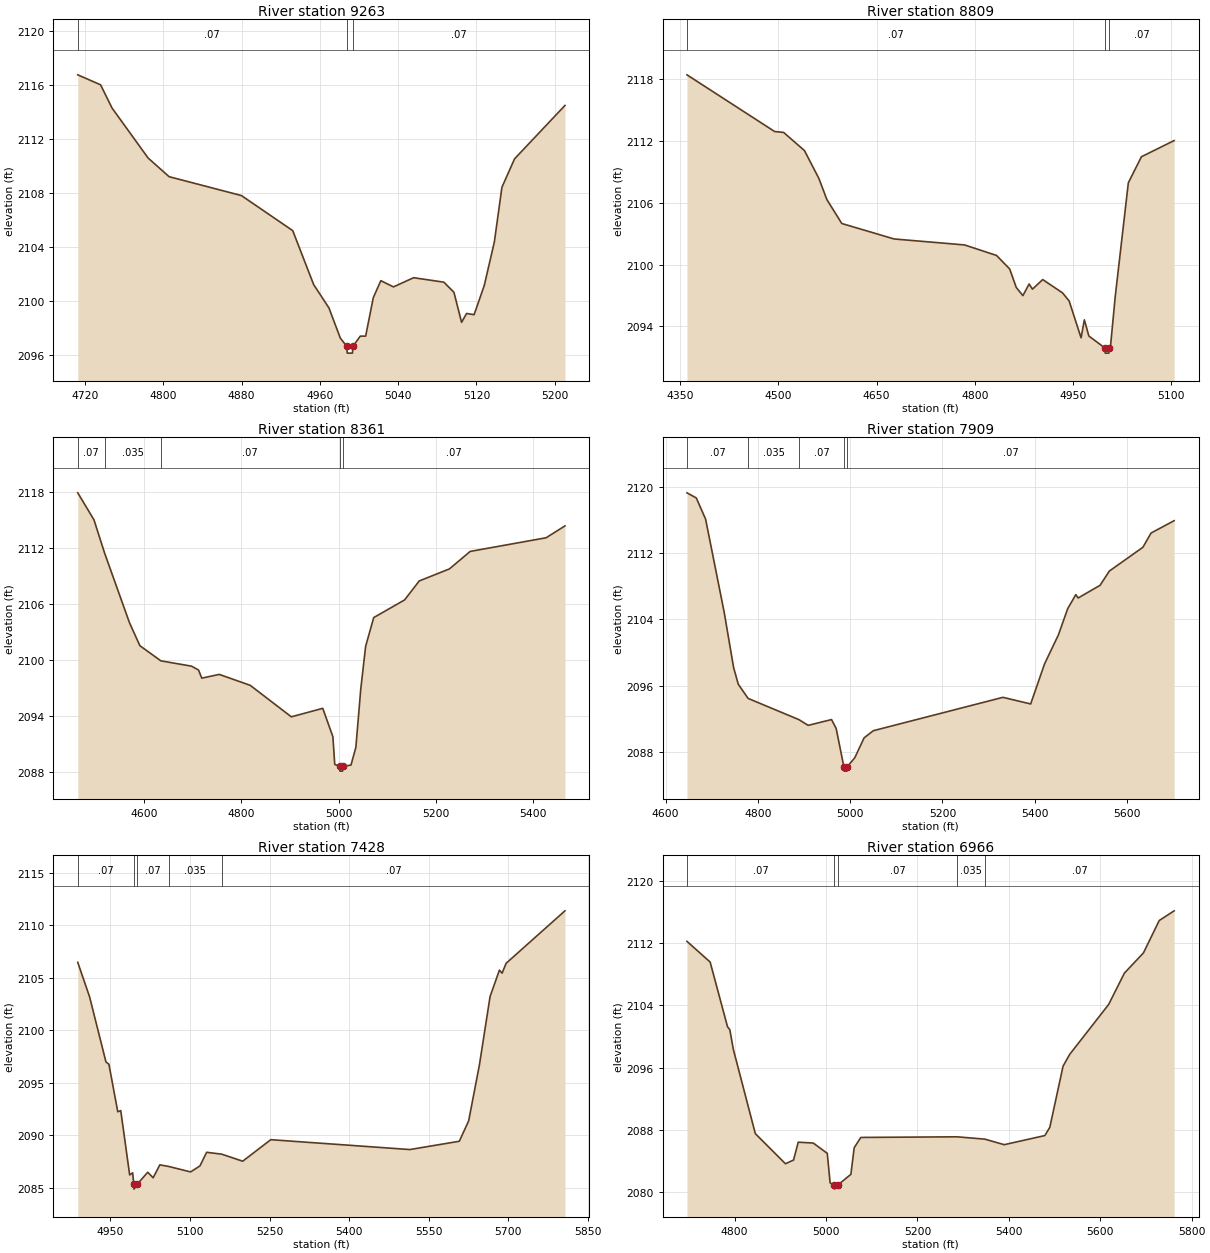
Type RM Length L Ch R = 1,9263,454,454,454
BEGIN DESCRIPTION:
Stream0358 19.0
END DESCRIPTION:
XS GIS Cut Line= 3
      1833975.01     13993025.01      1833725.00     13992875.00
      1833525.01     13992825.00
#Sta/Elev= 30
  4712.7 2116.74  4736.0 2116.00  4747.7 2114.28  4784.6 2110.57  4806.0 2109.19
  4879.9 2107.79  4932.3 2105.19  4953.7 2101.19  4969.3 2099.46  4980.9 2097.23
  4987.5 2096.61  4988.0 2096.11  4993.3 2096.11  4993.8 2096.61  5001.3 2097.37
  5006.8 2097.37  5014.6 2100.22  5022.3 2101.48  5035.2 2101.02  5055.8 2101.70
  5086.7 2101.37  5097.0 2100.62  5104.8 2098.39  5109.9 2099.05  5117.6 2098.96
  5128.0 2101.13  5138.3 2104.36  5146.0 2108.40  5158.9 2110.51  5210.4 2114.47
#Mann=3,-1,0
  4712.7    0.07       0  4987.5    0.05       0  4993.8    0.07       0
Bank Sta=4987.5,4993.8
Exp/Cntr=0.3,0.1

Type RM Length L Ch R = 1,8809,448,448,448
BEGIN DESCRIPTION:
Stream0358 18.0
END DESCRIPTION:
XS GIS Cut Line= 4
      1834099.53     13992872.32      1833896.82     13992503.64
      1833675.00     13992475.00      1833574.99     13992475.00
#Sta/Elev= 30
  4360.2 2118.41  4494.1 2112.91  4507.9 2112.82  4539.7 2111.06  4561.8 2108.35
  4574.0 2106.30  4596.8 2103.98  4676.7 2102.48  4784.4 2101.90  4833.2 2100.88
  4853.3 2099.57  4863.4 2097.77  4873.5 2096.98  4883.0 2098.11  4888.1 2097.61
  4903.8 2098.54  4934.0 2097.25  4944.1 2096.47  4962.4 2092.89  4967.4 2094.63
  4974.3 2093.06  4998.8 2091.90  4999.3 2091.40  5004.8 2091.40  5005.3 2091.90
  5007.1 2091.90  5014.6 2096.90  5034.6 2107.93  5054.6 2110.46  5104.6 2112.03
#Mann=3,-1,0
  4360.2    0.07       0  4998.8    0.05       0  5005.3    0.07       0
Bank Sta=4998.8,5005.3
Exp/Cntr=0.3,0.1

Type RM Length L Ch R = 1,8361,452,452,452
BEGIN DESCRIPTION:
Stream0358 17.0
END DESCRIPTION:
XS GIS Cut Line= 4
      1834225.03     13992425.03      1833825.00     13992075.00
      1833600.67     13992089.36      1833419.74     13992254.65
#Sta/Elev= 30
  4463.7 2117.90  4497.0 2115.01  4519.0 2111.43  4570.0 2104.00  4591.4 2101.54
  4634.6 2099.92  4697.7 2099.35  4711.9 2098.94  4718.6 2098.07  4754.6 2098.47
  4818.2 2097.30  4902.7 2093.93  4967.3 2094.84  4988.1 2091.80  4991.9 2088.84
  5002.0 2088.62  5002.5 2088.12  5008.0 2088.12  5008.5 2088.62  5025.3 2088.77
  5035.3 2090.66  5045.4 2096.90  5055.4 2101.47  5072.0 2104.55  5135.5 2106.44
  5165.6 2108.47  5227.7 2109.76  5270.3 2111.63  5426.3 2113.09  5465.1 2114.36
#Mann=5,-1,0
  4463.7    0.07       0  4519.0   0.035       0  4634.6    0.07       0
  5002.0    0.05       0  5008.5    0.07       0
Bank Sta=5002,5008.5
Exp/Cntr=0.3,0.1

Type RM Length L Ch R = 1,7909,481,481,481
BEGIN DESCRIPTION:
Stream0358 16.0
END DESCRIPTION:
XS GIS Cut Line= 3
      1834424.96     13991774.99      1834075.00     13991725.00
      1833375.00     13991675.00
#Sta/Elev= 30
  4646.5 2119.32  4666.7 2118.70  4686.9 2116.13  4727.3 2104.81  4747.5 2098.18
  4757.6 2096.16  4778.9 2094.44  4888.7 2091.88  4909.1 2091.18  4959.6 2091.88
  4969.7 2090.80  4986.5 2086.14  4987.0 2085.64  4992.9 2085.64  4993.4 2086.14
  5010.0 2087.26  5030.1 2089.66  5050.1 2090.53  5330.9 2094.57  5391.0 2093.77
  5421.1 2098.62  5451.2 2102.14  5471.2 2105.30  5488.8 2107.00  5493.8 2106.59
  5541.4 2108.13  5561.4 2109.85  5634.1 2112.73  5651.7 2114.45  5701.8 2115.95
#Mann=5,-1,0
  4646.5    0.07       0  4778.9   0.035       0  4888.7    0.07       0
  4986.5    0.05       0  4993.4    0.07       0
Bank Sta=4986.5,4993.4
Exp/Cntr=0.3,0.1

Type RM Length L Ch R = 1,7428,462,462,462
BEGIN DESCRIPTION:
Stream0358 15.0
END DESCRIPTION:
XS GIS Cut Line= 3
      1834374.97     13991374.99      1834275.00     13991325.00
      1833475.00     13991425.00
#Sta/Elev= 30
  4888.7 2106.47  4911.0 2103.18  4941.8 2096.99  4947.4 2096.76  4964.1 2092.24
  4969.7 2092.35  4986.5 2086.22  4992.1 2086.42  4994.2 2085.37  4994.7 2084.87
  5001.2 2085.37  5020.6 2086.48  5030.7 2085.95  5043.3 2087.18  5060.1 2087.03
  5101.3 2086.51  5118.9 2087.08  5131.5 2088.38  5159.9 2088.20  5199.5 2087.53
  5252.4 2089.58  5514.4 2088.64  5607.7 2089.43  5625.3 2091.38  5645.5 2096.69
  5665.6 2103.21  5683.2 2105.73  5688.3 2105.44  5695.8 2106.38  5806.7 2111.38
#Mann=5,-1,0
  4888.7    0.07       0  4994.2    0.05       0  5001.2    0.07       0
  5060.1   0.035       0  5159.9    0.07       0
Bank Sta=4994.2,5001.2
Exp/Cntr=0.3,0.1

Type RM Length L Ch R = 1,6966,484,484,484
BEGIN DESCRIPTION:
Stream0358 14.0
END DESCRIPTION:
XS GIS Cut Line= 3
      1834375.04     13990974.99      1834075.00     13991025.00
      1833374.96     13991325.02
#Sta/Elev= 30
  4695.9 2112.22  4746.6 2109.56  4784.6 2101.25  4789.7 2100.86  4797.3 2098.35
  4845.5 2087.51  4911.4 2083.65  4929.1 2084.13  4939.3 2086.42  4972.2 2086.31
  5002.8 2084.99  5009.1 2081.19  5018.3 2080.89  5018.8 2080.39  5025.3 2080.89
  5054.5 2082.29  5061.7 2085.70  5076.2 2087.03  5287.1 2087.11  5347.7 2086.81
  5389.9 2086.10  5478.8 2087.27  5489.7 2088.33  5518.7 2096.19  5533.2 2097.70
  5618.4 2104.11  5652.9 2108.14  5694.6 2110.74  5729.0 2114.89  5761.7 2116.14
#Mann=5,-1,0
  4695.9    0.07       0  5018.3    0.05       0  5025.3    0.07       0
  5287.1   0.035       0  5347.7    0.07       0
Bank Sta=5018.3,5025.3
Exp/Cntr=0.3,0.1

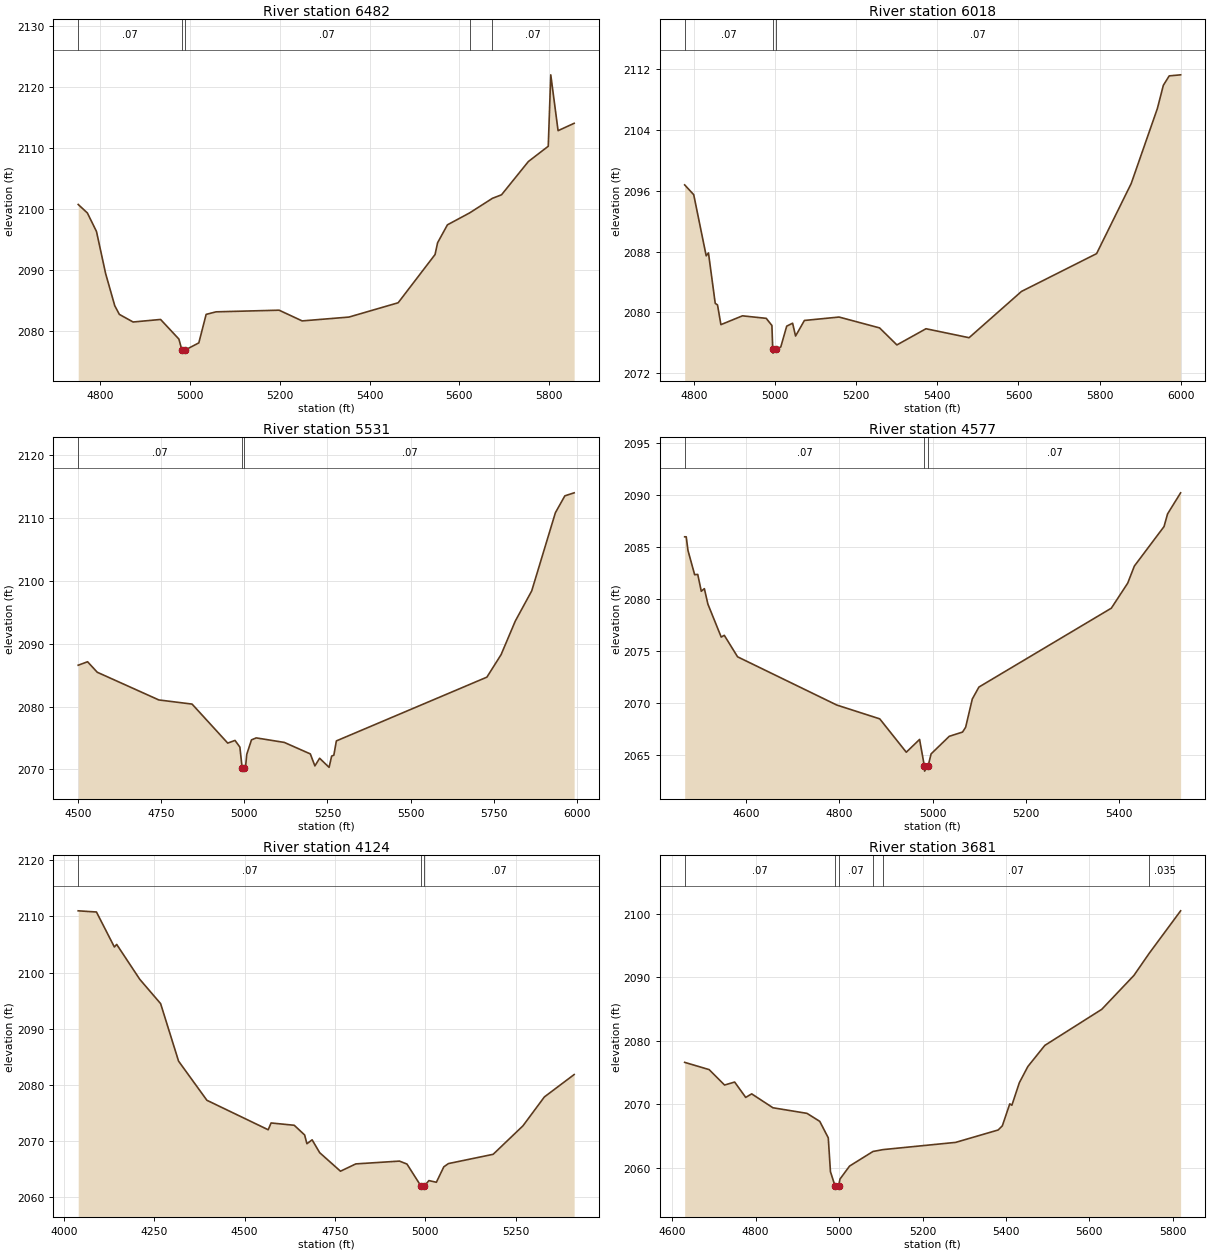
Type RM Length L Ch R = 1,6482,464,464,464
BEGIN DESCRIPTION:
Stream0358 13.0
END DESCRIPTION:
XS GIS Cut Line= 3
      1834324.95     13990525.01      1834075.00     13990575.00
      1833325.00     13990975.00
#Sta/Elev= 30
  4750.8 2100.70  4771.2 2099.31  4791.5 2096.27  4811.9 2089.35  4832.3 2084.06
  4842.5 2082.65  4873.1 2081.40  4934.3 2081.82  4975.1 2078.60  4981.8 2076.79
  4982.3 2076.29  4988.8 2076.79  5019.5 2077.97  5035.8 2082.65  5057.8 2083.07
  5198.4 2083.34  5249.7 2081.58  5353.9 2082.21  5463.6 2084.56  5545.8 2092.48
  5551.5 2094.42  5573.4 2097.36  5622.7 2099.31  5673.6 2101.71  5693.9 2102.29
  5753.7 2107.75  5798.0 2110.26  5803.6 2121.99  5819.9 2112.82  5855.7 2114.03
#Mann=5,-1,0
  4750.8    0.07       0  4981.8    0.05       0  4988.8    0.07       0
  5622.7   0.035       0  5673.6    0.07       0
Bank Sta=4981.8,4988.8
Exp/Cntr=0.3,0.1

Type RM Length L Ch R = 1,6018,487,487,487
BEGIN DESCRIPTION:
Stream0358 12.0
END DESCRIPTION:
XS GIS Cut Line= 3
      1834324.97     13990224.98      1834125.00     13990125.00
      1833324.97     13989524.98
#Sta/Elev= 30
  4776.4 2096.80  4798.7 2095.51  4829.5 2087.46  4835.1 2087.84  4851.8 2081.20
  4857.4 2081.00  4865.8 2078.40  4918.9 2079.56  4977.6 2079.23  4991.6 2078.29
  4993.7 2075.15  4994.2 2074.65  5000.7 2075.15  5013.5 2075.46  5028.1 2078.20
  5042.7 2078.59  5050.0 2076.90  5071.8 2078.95  5157.3 2079.40  5257.3 2077.97
  5300.0 2075.73  5371.8 2077.86  5478.1 2076.68  5607.3 2082.77  5792.7 2087.75
  5878.1 2096.98  5942.7 2106.86  5957.3 2109.90  5971.8 2111.15  6000.0 2111.29
#Mann=3,-1,0
  4776.4    0.07       0  4993.7    0.05       0  5000.7    0.07       0
Bank Sta=4993.7,5000.7
Exp/Cntr=0.3,0.1

Type RM Length L Ch R = 1,5531,954,954,954
BEGIN DESCRIPTION:
Stream0358 11.0
END DESCRIPTION:
XS GIS Cut Line= 3
      1834525.02     13990075.03      1834225.00     13989675.00
      1833475.01     13989025.01
#Sta/Elev= 30
  4500.0 2086.60  4528.2 2087.15  4557.3 2085.48  4742.7 2081.07  4842.7 2080.41
  4950.0 2074.20  4971.9 2074.63  4986.5 2073.57  4993.4 2070.24  4993.9 2069.74
  5000.4 2070.24  5003.3 2070.24  5007.2 2072.41  5021.4 2074.71  5035.7 2075.03
  5120.2 2074.31  5198.5 2072.48  5212.3 2070.57  5226.5 2071.79  5255.0 2070.34
  5262.7 2072.14  5269.3 2072.27  5276.9 2074.55  5729.9 2084.70  5772.6 2088.28
  5815.4 2093.63  5864.8 2098.43  5936.0 2110.87  5964.5 2113.56  5992.5 2114.04
#Mann=3,-1,0
  4500.0    0.07       0  4993.4    0.05       0  5000.4    0.07       0
Bank Sta=4993.4,5000.4
Exp/Cntr=0.3,0.1

Type RM Length L Ch R = 1,4577,453,453,453
BEGIN DESCRIPTION:
Stream0358 10.0
END DESCRIPTION:
XS GIS Cut Line= 3
      1834825.00     13989175.00      1834425.00     13988825.00
      1834025.01     13988475.01
#Sta/Elev= 30
  4468.5 2085.98  4471.8 2085.98  4475.6 2084.66  4489.9 2082.33  4496.5 2082.36
  4504.1 2080.74  4510.7 2080.99  4518.3 2079.50  4546.8 2076.33  4553.4 2076.50
  4581.9 2074.43  4794.5 2069.79  4886.6 2068.46  4943.5 2065.25  4972.0 2066.48
  4982.2 2063.93  4982.7 2063.43  4990.3 2063.93  4996.7 2065.09  5035.6 2066.78
  5064.1 2067.19  5070.7 2067.65  5085.0 2070.37  5099.2 2071.52  5383.0 2079.11
  5418.1 2081.52  5432.3 2083.16  5495.9 2086.96  5503.5 2088.18  5531.5 2090.21
#Mann=3,-1,0
  4468.5    0.07       0  4982.2    0.05       0  4990.3    0.07       0
Bank Sta=4982.2,4990.3
Exp/Cntr=0.3,0.1

Type RM Length L Ch R = 1,4124,443,443,443
BEGIN DESCRIPTION:
Stream0358 9.0
END DESCRIPTION:
XS GIS Cut Line= 3
      1835175.02     13989175.02      1834575.00     13988425.00
      1834175.01     13988325.00
#Sta/Elev= 30
  4039.5 2111.01  4090.0 2110.80  4139.6 2104.57  4146.0 2105.03  4210.0 2098.81
  4267.6 2094.49  4317.3 2084.25  4395.7 2077.28  4565.4 2072.03  4573.4 2073.24
  4637.4 2072.83  4666.2 2071.11  4672.6 2069.54  4687.0 2070.24  4707.9 2067.95
  4765.5 2064.65  4807.9 2065.95  4928.8 2066.45  4949.6 2065.92  4988.7 2061.96
  4989.2 2061.46  4996.8 2061.96  5010.3 2062.98  5030.9 2062.68  5051.5 2065.43
  5064.4 2066.01  5188.1 2067.66  5270.6 2072.73  5329.8 2077.87  5412.3 2081.86
#Mann=3,-1,0
  4039.5    0.07       0  4988.7    0.05       0  4996.8    0.07       0
Bank Sta=4988.7,4996.8
Exp/Cntr=0.3,0.1

Type RM Length L Ch R = 1,3681,469,469,469
BEGIN DESCRIPTION:
Stream0358 8.0
END DESCRIPTION:
XS GIS Cut Line= 3
      1835092.40     13988000.83      1834725.00     13988075.00
      1833925.05     13988224.99
#Sta/Elev= 30
  4629.9 2076.57  4688.5 2075.43  4725.5 2073.00  4749.7 2073.47  4776.2 2071.05
  4790.5 2071.61  4841.5 2069.42  4923.1 2068.54  4953.7 2067.28  4974.1 2064.68
  4979.3 2059.35  4990.3 2057.11  4990.8 2056.61  4998.8 2057.11  5002.2 2058.20
  5025.1 2060.24  5081.3 2062.54  5105.1 2062.83  5279.4 2063.97  5381.2 2065.92
  5391.3 2066.58  5409.1 2070.04  5414.2 2069.82  5432.0 2073.36  5452.4 2075.91
  5493.1 2079.24  5629.6 2084.92  5706.7 2090.26  5743.2 2093.73  5818.6 2100.43
#Mann=6,-1,0
  4629.9    0.07       0  4990.3    0.05       0  4998.8    0.07       0
  5081.3   0.035       0  5105.1    0.07       0  5743.2   0.035       0
Bank Sta=4990.3,4998.8
Exp/Cntr=0.3,0.1

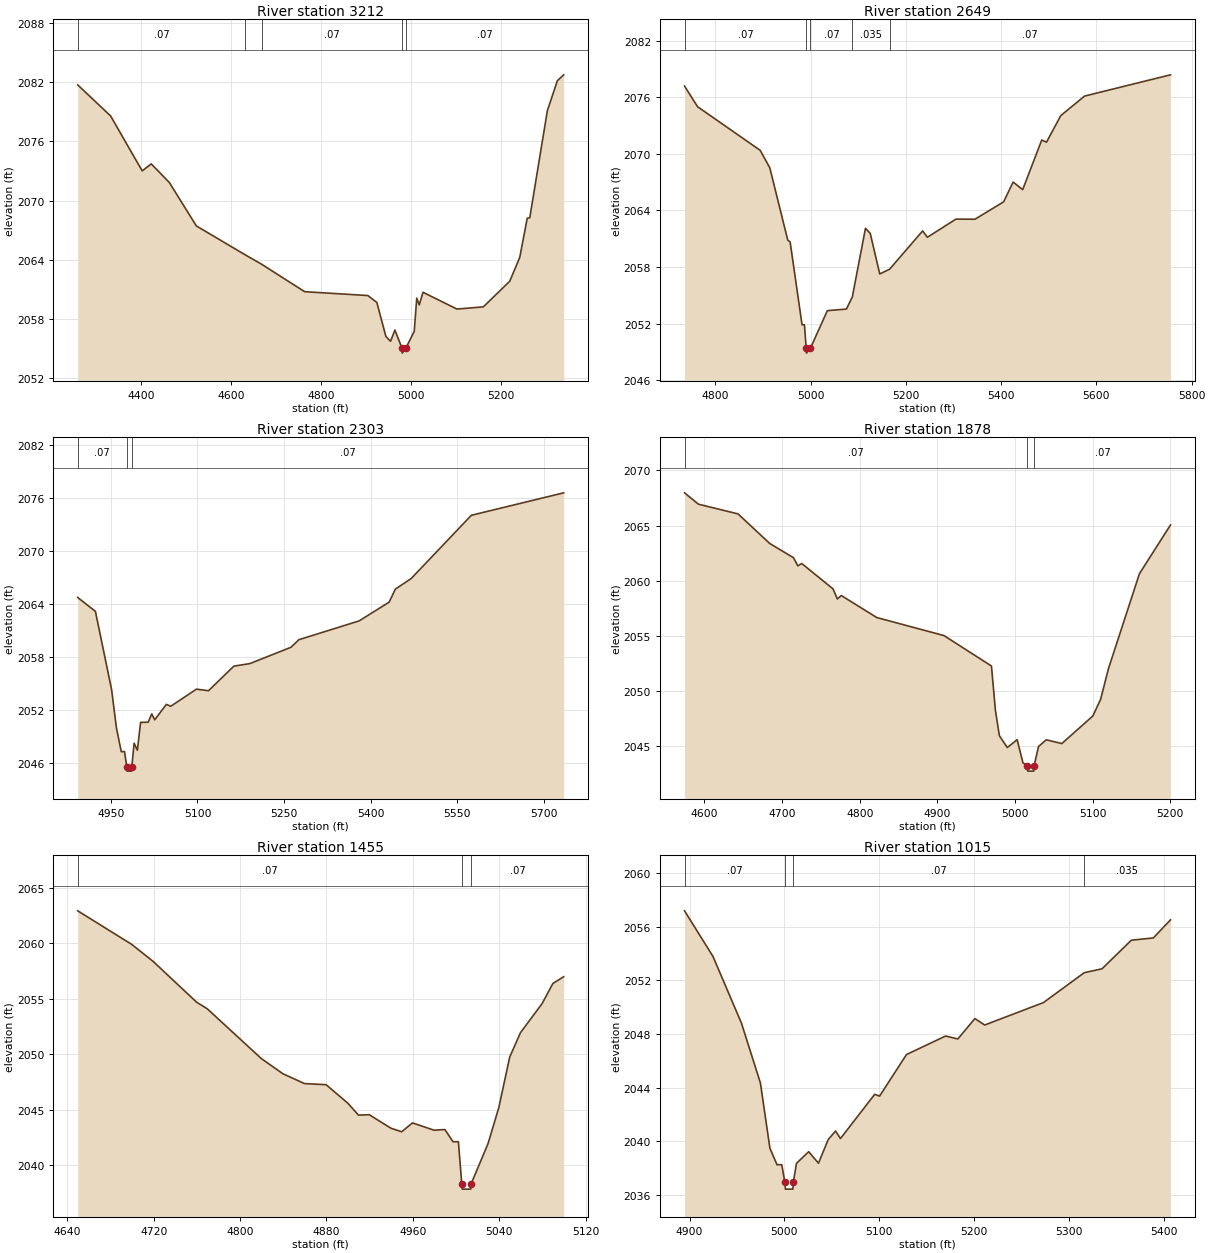
Type RM Length L Ch R = 1,3212,563,563,563
BEGIN DESCRIPTION:
Stream0358 7.0
END DESCRIPTION:
XS GIS Cut Line= 3
      1835267.92     13987606.33      1834525.00     13987675.00
      1834225.00     13987825.00
#Sta/Elev= 30
  4258.4 2081.74  4331.6 2078.59  4401.9 2073.02  4422.0 2073.73  4462.2 2071.85
  4522.4 2067.44  4631.0 2064.51  4667.8 2063.55  4763.5 2060.77  4904.1 2060.38
  4924.1 2059.68  4944.2 2056.23  4954.7 2055.74  4964.3 2056.88  4980.1 2055.04
  4980.6 2054.54  4988.7 2055.04  5007.3 2056.75  5012.9 2060.12  5018.5 2059.43
  5026.8 2060.71  5102.3 2059.01  5161.0 2059.23  5219.7 2061.82  5242.1 2064.24
  5258.8 2068.22  5264.4 2068.26  5303.6 2079.13  5325.9 2082.17  5339.9 2082.76
#Mann=5,-1,0
  4258.4    0.07       0  4631.0   0.035       0  4667.8    0.07       0
  4980.1    0.05       0  4988.7    0.07       0
Bank Sta=4980.1,4988.7
Exp/Cntr=0.3,0.1

Type RM Length L Ch R = 1,2649,346,346,346
BEGIN DESCRIPTION:
Stream0358 6.0
END DESCRIPTION:
XS GIS Cut Line= 3
      1835182.15     13987411.65      1834936.12     13987375.70
      1834164.69     13987369.02
#Sta/Elev= 30
  4735.5 2077.18  4762.9 2074.99  4894.3 2070.37  4914.5 2068.52  4952.1 2060.87
  4957.2 2060.65  4982.2 2051.88  4987.2 2051.88  4990.9 2049.38  4991.4 2048.88
  4999.6 2049.38  5035.3 2053.38  5075.3 2053.55  5087.7 2054.83  5115.3 2062.11
  5125.3 2061.57  5145.3 2057.27  5165.9 2057.77  5235.3 2061.83  5245.3 2061.16
  5305.3 2063.08  5345.3 2063.07  5405.3 2064.91  5425.3 2067.01  5445.3 2066.20
  5485.3 2071.46  5495.3 2071.23  5525.3 2074.05  5575.3 2076.12  5755.6 2078.37
#Mann=5,-1,0
  4735.5    0.07       0  4990.9    0.05       0  4999.6    0.07       0
  5087.7   0.035       0  5165.9    0.07       0
Bank Sta=4990.9,4999.6
Exp/Cntr=0.3,0.1

Type RM Length L Ch R = 1,2303,425,425,425
BEGIN DESCRIPTION:
Stream0358 5.0
END DESCRIPTION:
XS GIS Cut Line= 3
      1834975.00     13987025.00      1834875.00     13987075.00
      1834175.49     13987285.84
#Sta/Elev= 30
  4892.4 2064.76  4923.1 2063.18  4951.1 2054.32  4959.5 2049.98  4967.9 2047.26
  4973.5 2047.29  4977.5 2045.56  4978.0 2045.06  4985.7 2045.06  4986.2 2045.56
  4990.2 2048.23  4995.8 2047.43  5001.4 2050.59  5014.6 2050.61  5020.7 2051.55
  5025.9 2050.88  5046.0 2052.63  5053.7 2052.42  5098.2 2054.36  5119.1 2054.18
  5163.1 2056.97  5190.9 2057.26  5262.1 2059.11  5275.8 2059.97  5380.2 2062.10
  5432.3 2064.23  5442.9 2065.70  5470.5 2066.91  5574.7 2074.08  5734.8 2076.63
#Mann=3,-1,0
  4892.4    0.07       0  4977.5    0.05       0  4986.2    0.07       0
Bank Sta=4977.5,4986.2
Exp/Cntr=0.3,0.1

Type RM Length L Ch R = 1,1878,423,423,423
BEGIN DESCRIPTION:
Stream0358 4.0
END DESCRIPTION:
XS GIS Cut Line= 3
      1835092.55     13986641.19      1834675.00     13986725.00
      1834474.97     13986725.00
#Sta/Elev= 30
  4574.4 2067.97  4592.3 2066.94  4643.3 2066.06  4684.1 2063.38  4714.7 2062.09
  4720.3 2061.35  4725.4 2061.56  4765.7 2059.26  4771.2 2058.35  4776.3 2058.66
  4822.1 2056.66  4908.5 2055.03  4969.7 2052.27  4974.8 2048.25  4979.9 2045.95
  4990.1 2044.88  5002.8 2045.59  5010.3 2043.48  5015.9 2043.24  5016.4 2042.74
  5024.2 2042.74  5024.7 2043.24  5030.3 2044.97  5040.3 2045.58  5060.3 2045.24
  5100.3 2047.74  5110.3 2049.25  5120.3 2052.01  5160.3 2060.64  5200.3 2065.06
#Mann=3,-1,0
  4574.4    0.07       0  5015.9    0.05       0  5024.7    0.07       0
Bank Sta=5015.9,5024.7
Exp/Cntr=0.3,0.1

Type RM Length L Ch R = 1,1455,440,440,440
BEGIN DESCRIPTION:
Stream0358 3.0
END DESCRIPTION:
XS GIS Cut Line= 3
      1835024.96     13986375.00      1834675.00     13986375.00
      1834574.96     13986375.00
#Sta/Elev= 30
  4649.7 2062.95  4699.7 2059.92  4719.7 2058.37  4759.7 2054.71  4769.7 2054.10
  4819.7 2049.61  4839.7 2048.24  4859.7 2047.35  4879.7 2047.25  4899.7 2045.59
  4909.7 2044.50  4919.7 2044.54  4939.7 2043.32  4949.7 2043.00  4959.7 2043.80
  4979.7 2043.14  4989.7 2043.20  4997.2 2042.10  5002.2 2042.10  5005.3 2038.32
  5005.8 2037.82  5013.6 2037.82  5014.1 2038.32  5029.7 2041.94  5039.7 2045.21
  5049.7 2049.74  5059.7 2051.95  5079.7 2054.57  5089.7 2056.39  5099.7 2057.00
#Mann=3,-1,0
  4649.7    0.07       0  5005.3    0.05       0  5014.1    0.07       0
Bank Sta=5005.3,5014.1
Exp/Cntr=0.3,0.1

Type RM Length L Ch R = 1,1015,355,355,355
BEGIN DESCRIPTION:
Stream0358 2.0
END DESCRIPTION:
XS GIS Cut Line= 3
      1835024.96     13986025.00      1834925.00     13986025.00
      1834524.97     13986125.01
#Sta/Elev= 30
  4894.7 2057.17  4924.7 2053.77  4954.7 2048.80  4974.7 2044.34  4984.7 2039.48
  4992.2 2038.25  4997.2 2038.25  5000.5 2036.93  5001.0 2036.43  5008.9 2036.43
  5009.4 2036.93  5012.7 2038.35  5025.6 2039.22  5035.9 2038.36  5046.2 2040.13
  5053.9 2040.76  5059.1 2040.20  5095.2 2043.50  5100.3 2043.36  5128.7 2046.46
  5169.9 2047.84  5182.8 2047.62  5200.8 2049.14  5211.1 2048.66  5273.0 2050.33
  5316.1 2052.56  5334.8 2052.85  5365.7 2054.98  5388.9 2055.15  5407.0 2056.50
#Mann=4,-1,0
  4894.7    0.07       0  5000.5    0.05       0  5009.4    0.07       0
  5316.1   0.035       0
Bank Sta=5000.5,5009.4
Exp/Cntr=0.3,0.1