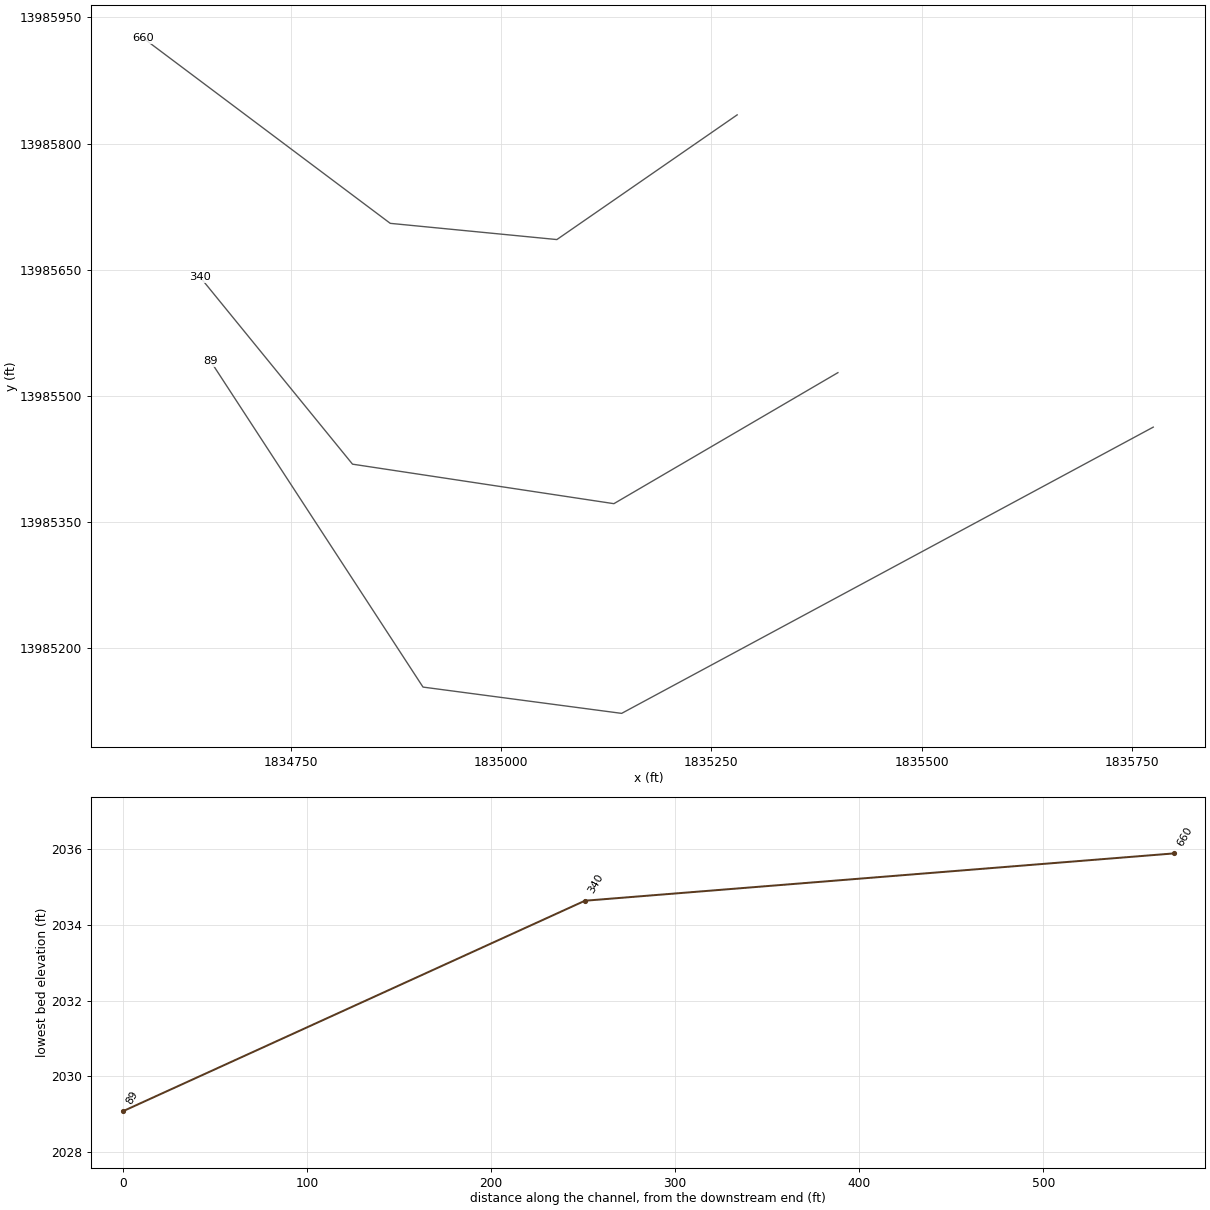
HEC-RAS study Stream0358.prj: Stream0358 Base Level Engineering

--- Stream0358.g01 (geometry) --- (continued)

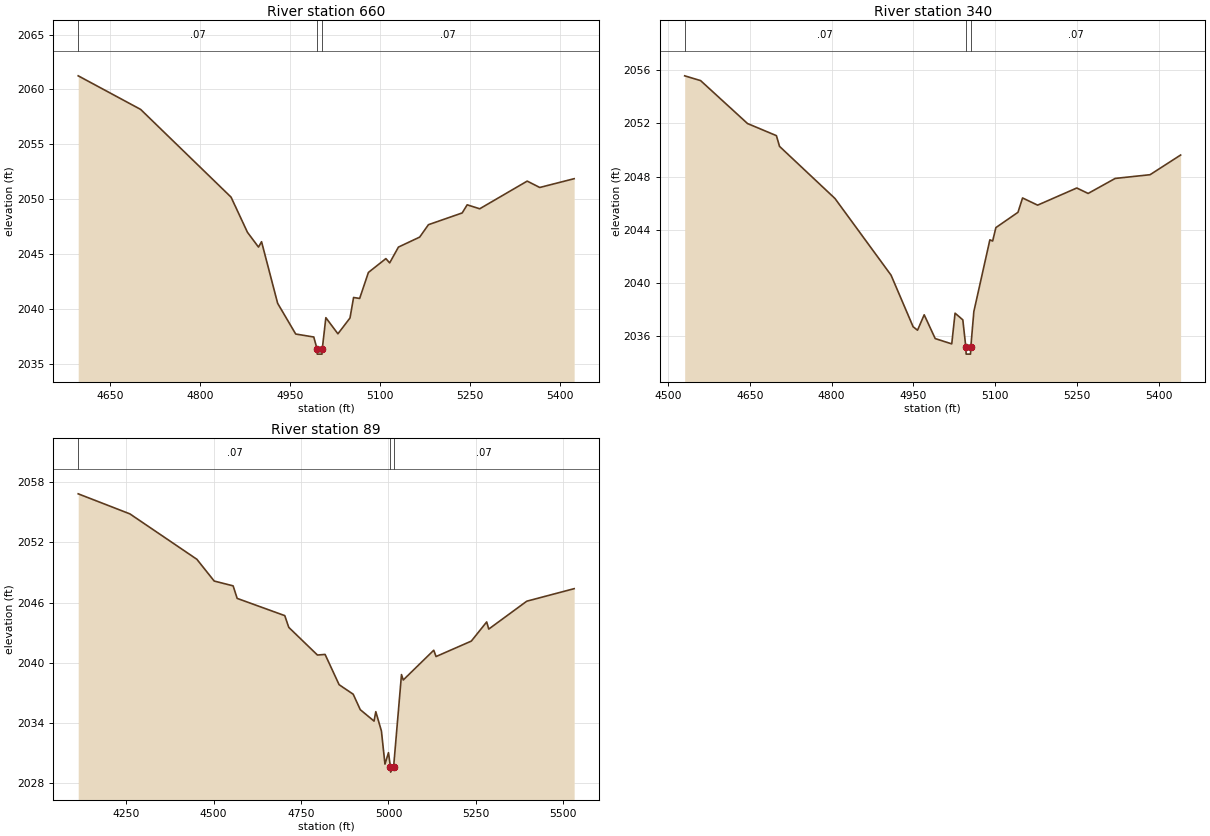
Type RM Length L Ch R = 1,660,320,320,320
BEGIN DESCRIPTION:
Stream0358 1.0
END DESCRIPTION:
XS GIS Cut Line= 4
      1835280.56     13985834.05      1835066.24     13985685.83
      1834868.20     13985705.10      1834574.97     13985925.02
#Sta/Elev= 30
  4597.2 2061.24  4701.2 2058.18  4851.8 2050.19  4879.1 2046.99  4897.5 2045.64
  4902.6 2046.13  4929.4 2040.52  4959.5 2037.72  4989.6 2037.45  4994.9 2036.39
  4995.4 2035.89  5003.3 2035.89  5003.8 2036.39  5009.7 2039.21  5029.8 2037.74
  5049.9 2039.18  5055.9 2041.05  5066.0 2040.96  5080.6 2043.33  5109.7 2044.59
  5116.0 2044.20  5130.6 2045.64  5166.0 2046.55  5180.6 2047.68  5236.8 2048.75
  5245.1 2049.49  5266.0 2049.13  5345.1 2051.65  5366.0 2051.07  5423.3 2051.87
#Mann=3,-1,0
  4597.2    0.07       0  4994.9    0.05       0  5003.8    0.07       0
Bank Sta=4994.9,5003.8
Exp/Cntr=0.3,0.1

Type RM Length L Ch R = 1,340,251,251,251
BEGIN DESCRIPTION:
Stream0358 0.0
END DESCRIPTION:
XS GIS Cut Line= 4
      1835400.31     13985527.63      1835134.01     13985371.89
      1834823.34     13985418.84      1834642.49     13985640.80
#Sta/Elev= 30
  4530.7 2055.58  4559.9 2055.22  4645.9 2051.99  4698.8 2051.08  4704.6 2050.27
  4806.2 2046.35  4909.0 2040.58  4949.4 2036.70  4957.5 2036.44  4969.7 2037.60
  4989.9 2035.81  5020.2 2035.41  5026.3 2037.72  5040.5 2037.22  5046.1 2035.14
  5046.6 2034.64  5054.6 2034.64  5055.1 2035.14  5060.7 2037.84  5090.1 2043.24
  5095.2 2043.15  5101.1 2044.16  5141.6 2045.31  5150.0 2046.39  5177.6 2045.85
  5249.4 2047.14  5270.2 2046.73  5319.8 2047.86  5383.7 2048.14  5439.7 2049.62
#Mann=3,-1,0
  4530.7    0.07       0  5046.1    0.05       0  5055.1    0.07       0
Bank Sta=5046.1,5055.1
Exp/Cntr=0.3,0.1

Type RM Length L Ch R = 1,89,0,0,0
BEGIN DESCRIPTION:
Stream0358 0.1
END DESCRIPTION:
XS GIS Cut Line= 4
      1835775.16     13985462.88      1835143.24     13985122.62
      1834907.13     13985153.87      1834654.57     13985541.36
#Sta/Elev= 30
  4112.6 2056.84  4260.4 2054.84  4452.0 2050.31  4501.5 2048.14  4555.7 2047.66
  4567.2 2046.41  4703.4 2044.69  4714.8 2043.52  4796.8 2040.76  4818.7 2040.82
  4858.8 2037.80  4899.1 2036.85  4919.3 2035.31  4958.7 2034.17  4963.7 2035.11
  4979.8 2033.18  4989.9 2029.88  5000.0 2031.02  5005.6 2029.58  5006.1 2029.08
  5014.6 2029.58  5037.2 2038.81  5042.2 2038.27  5129.5 2041.24  5136.0 2040.61
  5236.9 2042.15  5280.8 2044.06  5286.8 2043.35  5395.5 2046.13  5531.0 2047.38
#Mann=3,-1,0
  4112.6    0.07       0  5005.6    0.05       0  5014.6    0.07       0
Bank Sta=5005.6,5014.6
Exp/Cntr=0.3,0.1

Chan Stop Cuts=-1