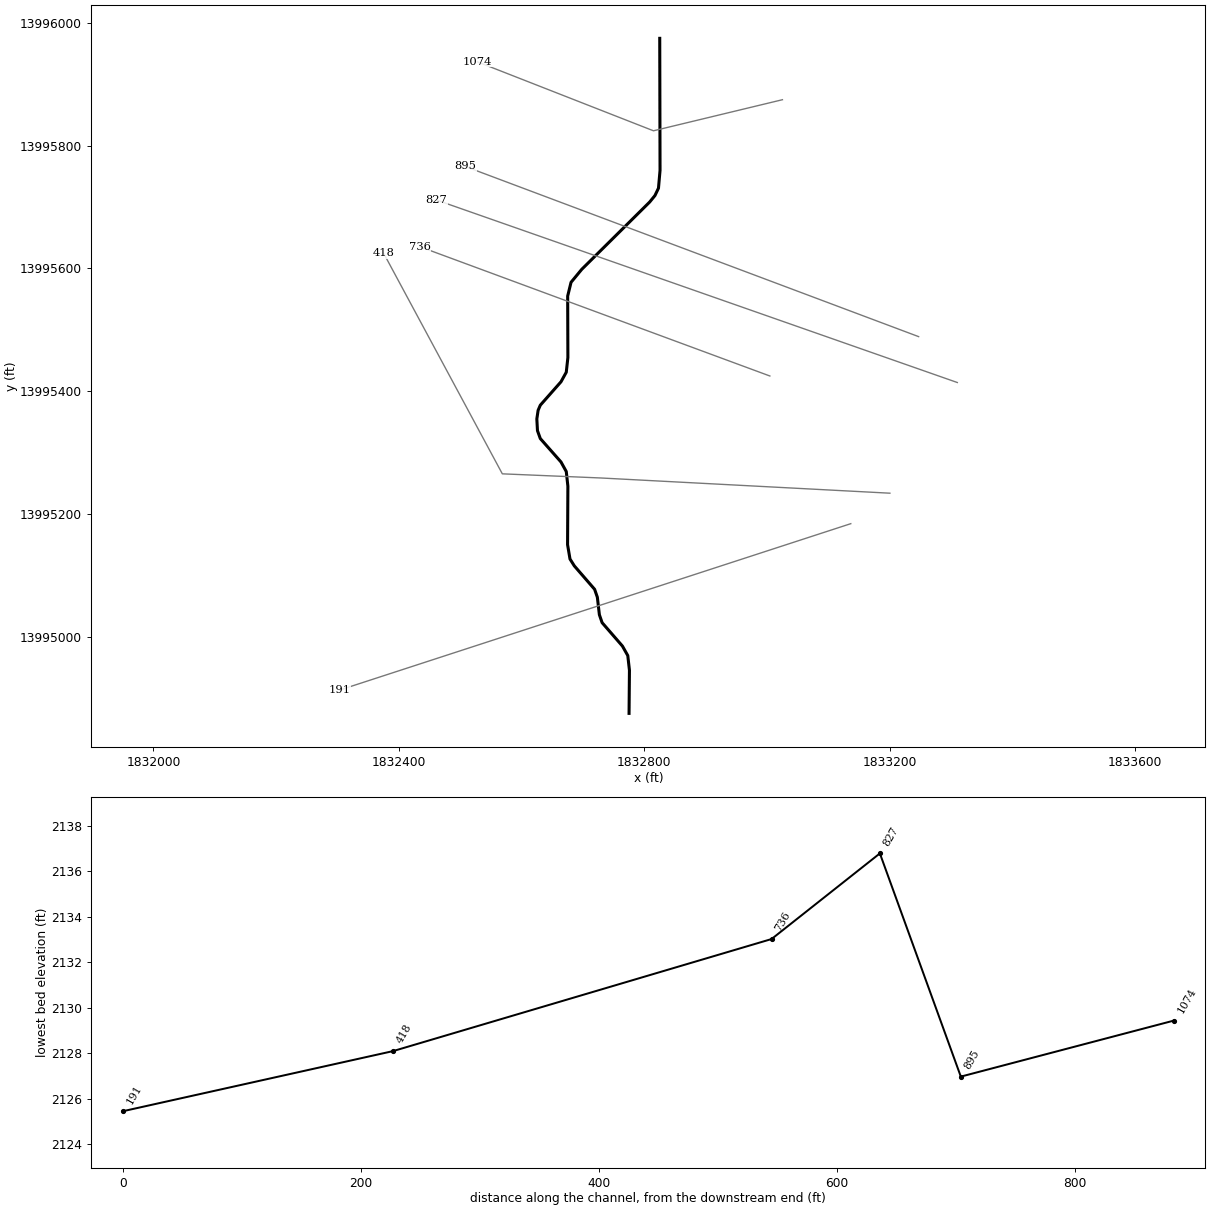
--- Stream0359.prj (project) ---

Proj Title=Stream0359 Base Level Engineering
Current Plan=p01
Default Exp/Contr=0.3,0.1
English Units
Geom File=g01
Flow File=f01
Plan File=p01
BEGIN DESCRIPTION:
Stream0359
END DESCRIPTION:

--- Stream0359.p01 (plan) ---

Plan Title=Multiple Run
Short Identifier=Multiple
Geom File=g01
Flow File=f01
Subcritical Flow
K Sum by GR= 0
Std Step Tol= 0.01
Critical Tol= 0.01
Num of Std Step Trials= 20
Max Error Tol= 0.3
Flow Tol Ratio= 0.001
Split Flow NTrial= 30
Split Flow Tol= 0.02
Split Flow Ratio= 0.02
Log Output Level= 0
Friction Slope Method= 1
Unsteady Friction Slope Method= 2
Unsteady Bridges Friction Slope Method= 1
Parabolic Critical Depth
Global Vel Dist=  1 , 1 , 1
Global Log Level= 0
CheckData=True
Encroach Param= -1, 0, 0, 0
BEGIN DESCRIPTION:
Multiple Run
END DESCRIPTION:

--- Stream0359.f01 (steady flow) ---

Flow Title=Multiple
Number of Profiles=7
Profile Names=10-year,25-year,50-year,1pct_min,100-year,1pct_plu,500-year
River Rch & RM= Stream0359,Reach-1,1074
     496     801    1077     701    1399    2791    2328
Boundary for River Rch & Prof#=Stream0359,Reach-1,1
Up Type=0
Dn Type=3
Dn Slope=0.005
Boundary for River Rch & Prof#=Stream0359,Reach-1,2
Up Type=0
Dn Type=3
Dn Slope=0.005
Boundary for River Rch & Prof#=Stream0359,Reach-1,3
Up Type=0
Dn Type=3
Dn Slope=0.005
Boundary for River Rch & Prof#=Stream0359,Reach-1,4
Up Type=0
Dn Type=3
Dn Slope=0.005
Boundary for River Rch & Prof#=Stream0359,Reach-1,5
Up Type=0
Dn Type=3
Dn Slope=0.005
Boundary for River Rch & Prof#=Stream0359,Reach-1,6
Up Type=0
Dn Type=3
Dn Slope=0.005
Boundary for River Rch & Prof#=Stream0359,Reach-1,7
Up Type=0
Dn Type=3
Dn Slope=0.005

--- Stream0359.g01 (geometry) ---

Geom Title=Existing Conditions

River Reach=Stream0359,Reach-1
Reach XY= 30
      1832825.00     13995975.00      1832825.49     13995759.80
      1832822.94     13995730.85      1832817.19     13995718.81
      1832808.57     13995708.24      1832697.86     13995598.53
      1832680.47     13995577.45      1832674.98     13995555.01
      1832675.32     13995454.86      1832672.70     13995430.93
      1832664.09     13995415.33      1832630.38     13995377.18
      1832626.82     13995368.88      1832624.72     13995354.82
      1832625.77     13995335.69      1832630.38     13995322.82
      1832664.09     13995284.67      1832672.70     13995269.07
      1832675.32     13995245.14      1832674.81     13995149.92
      1832678.76     13995126.56      1832685.80     13995115.33
      1832718.88     13995077.18      1832723.33     13995064.31
      1832726.66     13995035.69      1832731.09     13995022.81
      1832764.21     13994984.67      1832772.93     13994969.14
      1832775.64     13994945.27      1832775.00     13994875.00

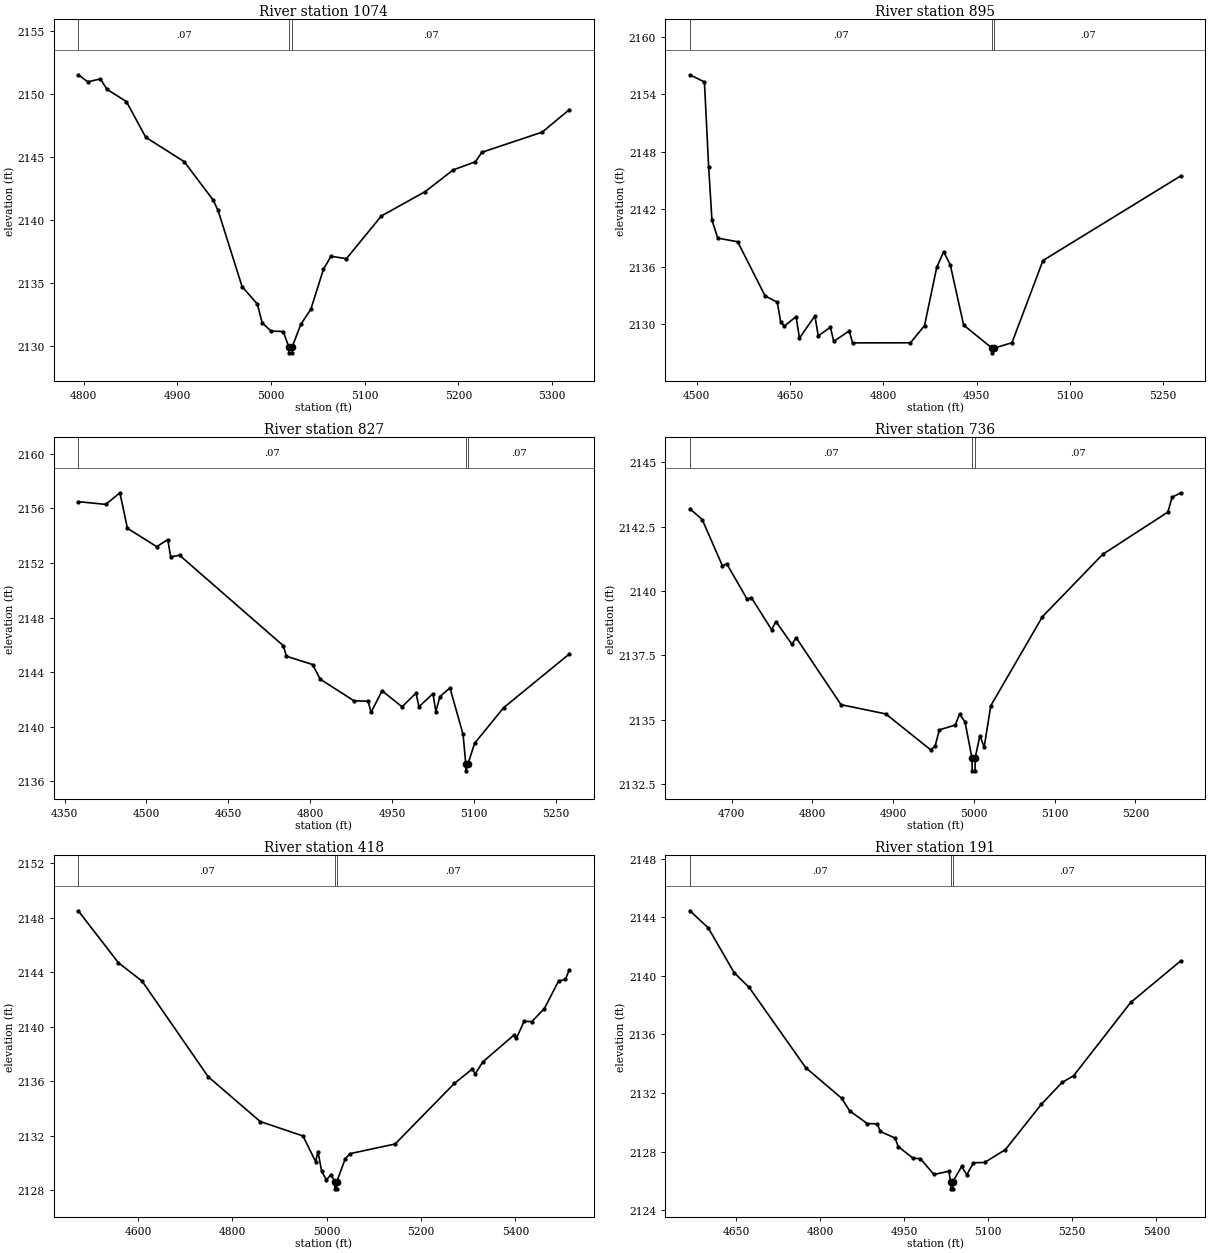
Type RM Length L Ch R = 1,1074,179,179,179
BEGIN DESCRIPTION:
Stream0359 2.0
END DESCRIPTION:
XS GIS Cut Line= 3
      1833024.96     13995874.99      1832814.80     13995824.34
      1832528.17     13995936.59
#Sta/Elev= 30
  4794.4 2151.51  4804.6 2150.95  4817.9 2151.18  4825.2 2150.35  4845.8 2149.38
  4866.4 2146.55  4907.5 2144.61  4938.4 2141.56  4943.6 2140.74  4969.2 2134.70
  4985.5 2133.31  4990.7 2131.82  5000.1 2131.17  5013.2 2131.13  5018.9 2129.94
  5019.2 2129.44  5022.7 2129.44  5022.9 2129.94  5031.8 2131.69  5042.6 2132.90
  5056.1 2136.08  5064.1 2137.10  5080.6 2136.92  5117.8 2140.30  5164.7 2142.24
  5194.5 2143.96  5218.1 2144.60  5225.2 2145.36  5289.6 2146.96  5318.4 2148.74
#Mann=3,-1,0
  4794.4    0.07       0  5018.9    0.05       0  5022.9    0.07       0
Bank Sta=5018.9,5022.9
Exp/Cntr=0.3,0.1

Type RM Length L Ch R = 1,895,68,68,68
BEGIN DESCRIPTION:
Stream0359 1.3
END DESCRIPTION:
XS GIS Cut Line= 2
      1833246.90     13995488.90      1832508.12     13995766.18
#Sta/Elev= 30
  4489.2 2156.04  4512.6 2155.29  4519.4 2146.38  4524.7 2140.85  4534.0 2138.97
  4566.0 2138.59  4610.1 2132.93  4629.7 2132.27  4635.0 2130.25  4640.8 2129.76
  4659.9 2130.77  4665.3 2128.52  4690.2 2130.84  4695.5 2128.75  4715.1 2129.66
  4720.4 2128.18  4745.3 2129.27  4750.7 2128.02  4843.7 2128.03  4866.3 2129.82
  4885.9 2135.90  4897.1 2137.55  4907.8 2136.15  4929.2 2129.88  4974.7 2127.48
  4974.9 2126.98  4978.7 2127.48  5006.9 2128.04  5056.7 2136.63  5278.3 2145.48
#Mann=3,-1,0
  4489.2    0.07       0  4974.7    0.05       0  4978.7    0.07       0
Bank Sta=4974.7,4978.7
Exp/Cntr=0.3,0.1

Type RM Length L Ch R = 1,827,91,91,91
BEGIN DESCRIPTION:
Stream0359 S
END DESCRIPTION:
XS GIS Cut Line= 2
      1833309.93     13995414.14      1832461.41     13995711.44
#Sta/Elev= 30
  4375.2 2156.48  4425.6 2156.28  4451.4 2157.13  4465.2 2154.53  4518.7 2153.19
  4539.1 2153.70  4544.4 2152.44  4560.6 2152.56  4750.9 2145.93  4756.2 2145.17
  4804.3 2144.56  4818.2 2143.49  4880.3 2141.90  4906.0 2141.88  4911.3 2141.05
  4931.4 2142.64  4968.0 2141.47  4993.7 2142.47  4999.0 2141.47  5024.7 2142.43
  5030.0 2141.12  5037.4 2142.21  5055.8 2142.85  5079.8 2139.45  5084.8 2137.28
  5085.0 2136.78  5088.8 2137.28  5101.0 2138.80  5154.1 2141.40  5274.3 2145.33
#Mann=3,-1,0
  4375.2    0.07       0  5084.8    0.05       0  5088.8    0.07       0
Bank Sta=5084.8,5088.8
Exp/Cntr=0.3,0.1

Type RM Length L Ch R = 1,736,318,318,318
BEGIN DESCRIPTION:
Stream0359 1.1
END DESCRIPTION:
XS GIS Cut Line= 2
      1833004.46     13995424.77      1832434.31     13995635.36
#Sta/Elev= 30
  4648.4 2143.20  4663.7 2142.78  4688.7 2140.98  4694.1 2141.06  4719.2 2139.69
  4724.5 2139.75  4749.6 2138.50  4754.9 2138.82  4774.7 2137.94  4780.0 2138.19
  4835.5 2135.59  4891.0 2135.23  4946.3 2133.84  4951.9 2133.97  4957.2 2134.61
  4977.0 2134.80  4982.3 2135.23  4989.0 2134.92  4997.6 2133.52  4997.9 2133.02
  5001.4 2133.02  5001.6 2133.52  5007.4 2134.39  5012.7 2133.94  5020.9 2135.55
  5084.9 2139.01  5159.5 2141.43  5240.1 2143.07  5245.4 2143.65  5256.2 2143.82
#Mann=3,-1,0
  4648.4    0.07       0  4997.6    0.05       0  5001.6    0.07       0
Bank Sta=4997.6,5001.6
Exp/Cntr=0.3,0.1

Type RM Length L Ch R = 1,418,227,227,227
BEGIN DESCRIPTION:
Stream0359 1.0
END DESCRIPTION:
XS GIS Cut Line= 4
      1833200.08     13995233.79      1832728.94     13995258.59
      1832568.49     13995265.34      1832375.00     13995625.01
#Sta/Elev= 30
  4473.5 2148.50  4558.7 2144.68  4608.8 2143.34  4749.0 2136.32  4859.1 2133.04
  4949.8 2131.98  4976.6 2130.10  4981.6 2130.83  4989.3 2129.41  4999.3 2128.75
  5009.3 2129.15  5017.3 2128.60  5017.5 2128.10  5021.0 2128.10  5021.3 2128.60
  5039.3 2130.30  5049.3 2130.68  5145.1 2131.39  5270.9 2135.84  5309.0 2136.90
  5314.7 2136.52  5330.9 2137.41  5396.6 2139.37  5402.3 2139.15  5418.5 2140.38
  5434.8 2140.37  5461.5 2141.32  5491.6 2143.35  5506.2 2143.46  5514.3 2144.18
#Mann=3,-1,0
  4473.5    0.07       0  5017.3    0.05       0  5021.3    0.07       0
Bank Sta=5017.3,5021.3
Exp/Cntr=0.3,0.1

Type RM Length L Ch R = 1,191,0,0,0
BEGIN DESCRIPTION:
Stream0359 T
END DESCRIPTION:
XS GIS Cut Line= 2
      1833136.33     13995184.13      1832302.97     13994912.85
#Sta/Elev= 30
  4567.4 2144.44  4600.3 2143.27  4646.5 2140.21  4673.2 2139.21  4774.2 2133.73
  4838.1 2131.65  4852.7 2130.78  4884.3 2129.91  4901.9 2129.90  4907.2 2129.38
  4933.9 2128.92  4939.1 2128.35  4965.8 2127.55  4978.9 2127.52  5003.0 2126.44
  5029.6 2126.66  5032.9 2125.96  5033.2 2125.46  5036.7 2125.46  5036.9 2125.96
  5052.6 2126.99  5061.6 2126.42  5073.6 2127.24  5093.5 2127.26  5130.7 2128.14
  5194.5 2131.22  5231.7 2132.72  5252.4 2133.18  5354.2 2138.18  5443.8 2141.03
#Mann=3,-1,0
  4567.4    0.07       0  5032.9    0.05       0  5036.9    0.07       0
Bank Sta=5032.9,5036.9
Exp/Cntr=0.3,0.1

Chan Stop Cuts=-1