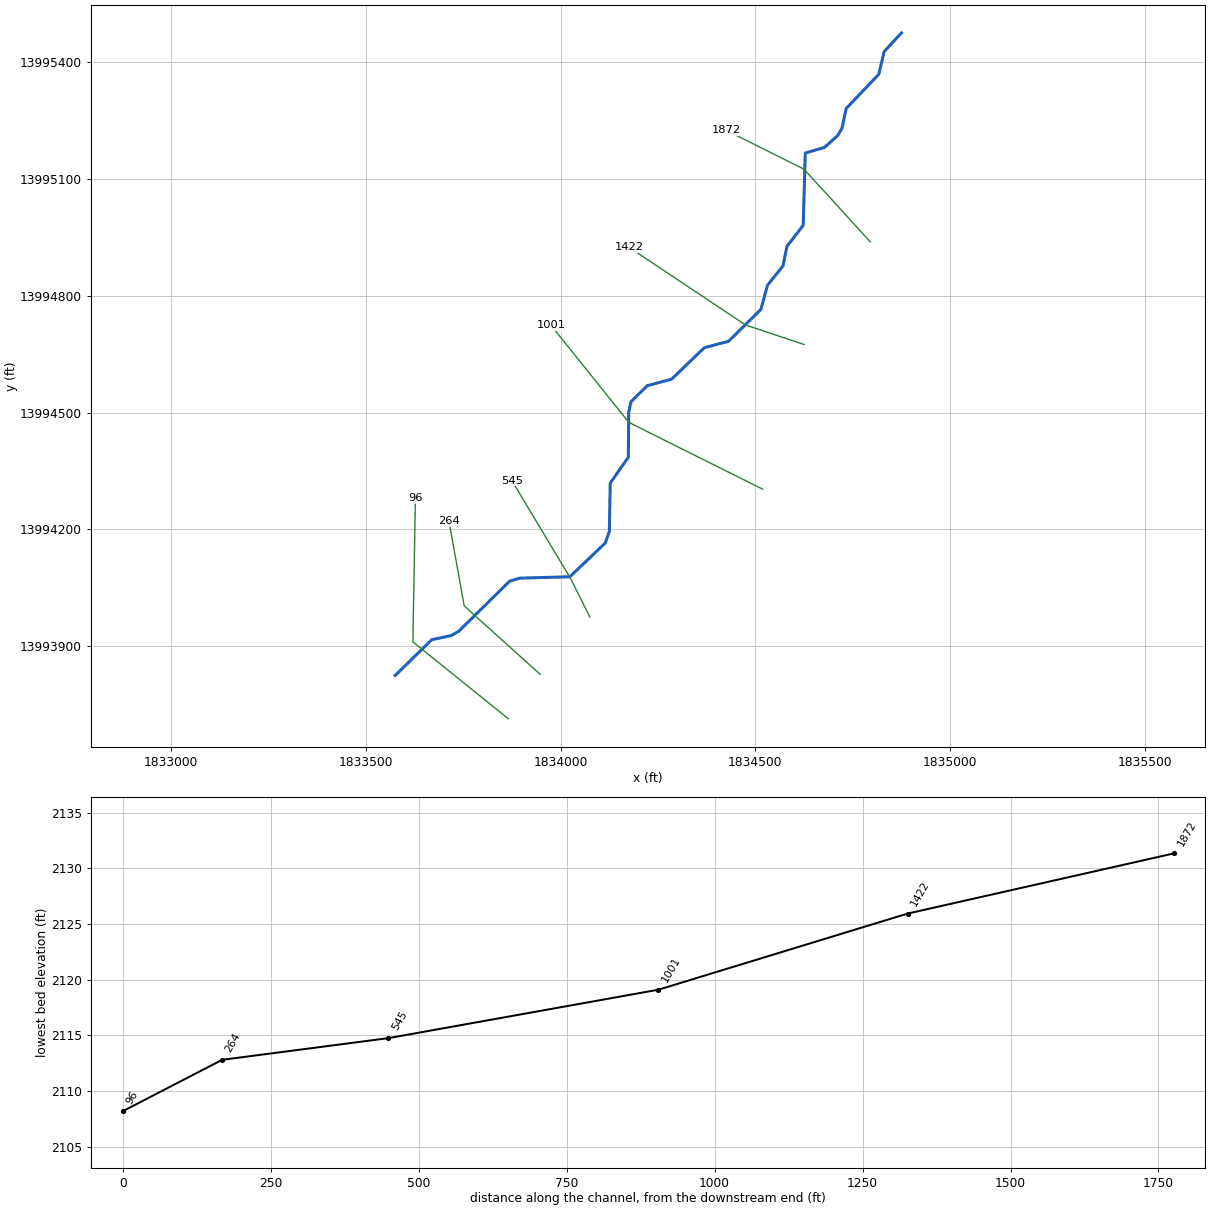
--- Stream0360.prj (project) ---

Proj Title=Stream0360 Base Level Engineering
Current Plan=p01
Default Exp/Contr=0.3,0.1
English Units
Geom File=g01
Flow File=f01
Plan File=p01
Y Axis Title=Elevation
X Axis Title(PF)=Main Channel Distance
X Axis Title(XS)=Station
BEGIN DESCRIPTION:
Stream0360
END DESCRIPTION:
DSS Export Rating Curves= 0
DSS Export Rating Curve Sorted= 0
DSS Export Volume Flow Curves= 0
DXF OffsetX= 0
DXF OffsetY= 0
DXF ScaleX= 1
DXF ScaleY= 10

--- Stream0360.p01 (plan) ---

Plan Title=Multiple Run
Short Identifier=Multiple
Geom File=g01
Flow File=f01
Subcritical Flow
K Sum by GR= 0
Std Step Tol= 0.01
Critical Tol= 0.01
Num of Std Step Trials= 20
Max Error Tol= 0.3
Flow Tol Ratio= 0.001
Split Flow NTrial= 30
Split Flow Tol= 0.02
Split Flow Ratio= 0.02
Log Output Level= 0
Friction Slope Method= 1
Unsteady Friction Slope Method= 2
Unsteady Bridges Friction Slope Method= 1
Parabolic Critical Depth
Global Vel Dist=  1 , 1 , 1
Global Log Level= 0
CheckData=True
Encroach Param= -1, 0, 0, 0
BEGIN DESCRIPTION:
Multiple Run
END DESCRIPTION:

--- Stream0360.f01 (steady flow) ---

Flow Title=Multiple
Program Version=4.10
Number of Profiles= 7
Profile Names=10-year,25-year,50-year,1pct_min,100-year,1pct_plu,500-year
River Rch & RM=Stream0360,Reach-1         ,1872
     858    1440    1984    1322    2637    5262    4601
Boundary for River Rch & Prof#=Stream0360,Reach-1         , 1
Up Type= 0
Dn Type= 3
Dn Slope=0.01
Boundary for River Rch & Prof#=Stream0360,Reach-1         , 2
Up Type= 0
Dn Type= 3
Dn Slope=0.01
Boundary for River Rch & Prof#=Stream0360,Reach-1         , 3
Up Type= 0
Dn Type= 3
Dn Slope=0.01
Boundary for River Rch & Prof#=Stream0360,Reach-1         , 4
Up Type= 0
Dn Type= 3
Dn Slope=0.01
Boundary for River Rch & Prof#=Stream0360,Reach-1         , 5
Up Type= 0
Dn Type= 3
Dn Slope=0.01
Boundary for River Rch & Prof#=Stream0360,Reach-1         , 6
Up Type= 0
Dn Type= 3
Dn Slope=0.01
Boundary for River Rch & Prof#=Stream0360,Reach-1         , 7
Up Type= 0
Dn Type= 3
Dn Slope=0.01
DSS Import GetInterval= 0
DSS Import GetPeak= 0
DSS Import FillOption= 0

--- Stream0360.g01 (geometry) ---

Geom Title=Existing Conditions

River Reach=Stream0360,Reach-1
Reach XY= 30
      1834875.00     13995475.00      1834830.70     13995427.35
      1834816.93     13995368.92      1834733.18     13995281.02
      1834722.52     13995230.88      1834711.44     13995211.47
      1834677.14     13995180.92      1834628.09     13995166.69
      1834622.76     13994980.93      1834581.12     13994927.18
      1834570.84     13994876.72      1834531.10     13994827.18
      1834514.24     13994765.30      1834431.07     13994683.15
      1834368.96     13994666.82      1834284.65     13994585.81
      1834222.42     13994569.26      1834180.36     13994527.70
      1834174.69     13994500.20      1834173.77     13994385.51
      1834127.27     13994319.06      1834125.02     13994194.99
      1834114.53     13994165.18      1834023.54     13994078.54
      1833894.99     13994075.02      1833868.81     13994067.18
      1833738.21     13993938.63      1833718.96     13993927.52
      1833668.93     13993916.89      1833575.00     13993825.00

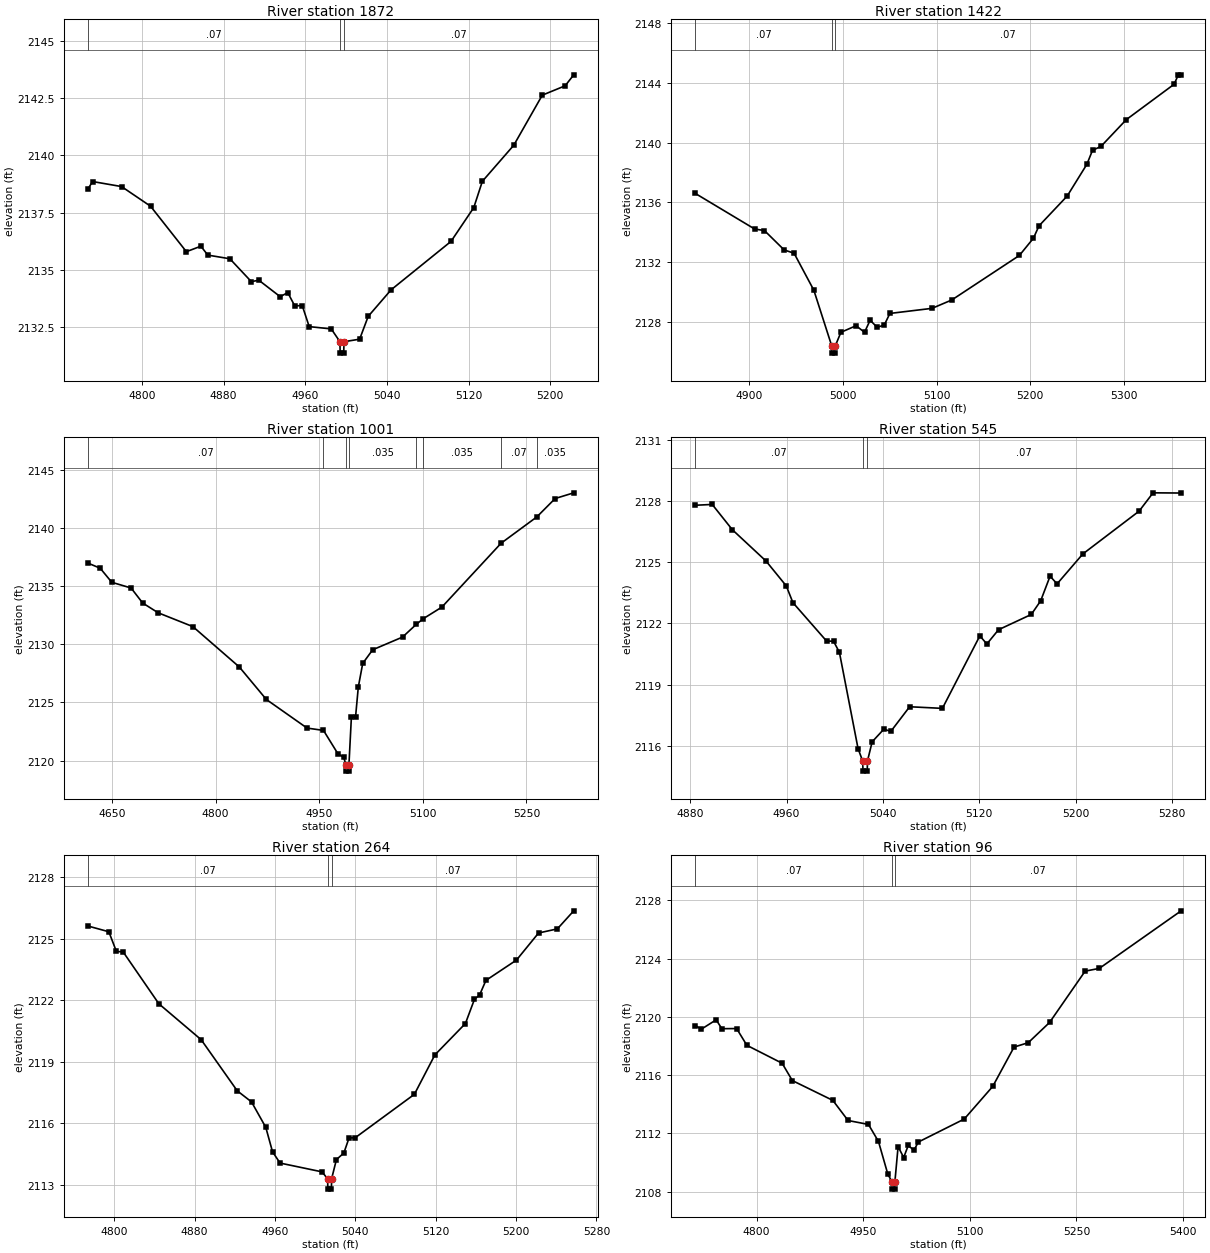
Type RM Length L Ch R = 1,1872,450,450,450
BEGIN DESCRIPTION:
Stream0360 4.0
END DESCRIPTION:
XS GIS Cut Line= 3
      1834794.97     13994938.72      1834625.00     13995125.00
      1834424.98     13995225.01
#Sta/Elev= 30
  4747.2 2138.53  4751.7 2138.86  4780.1 2138.64  4808.5 2137.78  4843.6 2135.79
  4857.8 2136.03  4864.6 2135.64  4886.2 2135.48  4907.2 2134.48  4914.6 2134.54
  4935.5 2133.82  4942.9 2134.00  4949.7 2133.42  4957.1 2133.43  4963.9 2132.51
  4985.5 2132.41  4994.0 2131.85  4994.2 2131.35  4997.7 2131.35  4998.0 2131.85
  5013.3 2131.96  5021.7 2132.96  5044.1 2134.12  5102.8 2136.24  5125.1 2137.72
  5133.5 2138.87  5164.3 2140.45  5192.2 2142.64  5214.6 2143.05  5223.0 2143.53
#Mann=3,-1,0
  4747.2    0.07       0  4994.0    0.05       0  4998.0    0.07       0
Bank Sta=4994,4998
Exp/Cntr=0.3,0.1

Type RM Length L Ch R = 1,1422,421,421,421
BEGIN DESCRIPTION:
Stream0360 3.0
END DESCRIPTION:
XS GIS Cut Line= 3
      1834624.97     13994675.01      1834475.00     13994725.00
      1834175.03     13994924.98
#Sta/Elev= 30
  4842.4 2136.60  4905.6 2134.23  4916.2 2134.12  4937.2 2132.83  4947.8 2132.61
  4968.9 2130.14  4987.9 2126.44  4988.2 2125.94  4991.7 2125.94  4991.9 2126.44
  4997.8 2127.33  5014.0 2127.77  5023.0 2127.33  5029.0 2128.14  5036.5 2127.66
  5044.1 2127.82  5050.1 2128.59  5095.1 2128.93  5116.2 2129.49  5188.3 2132.46
  5203.3 2133.61  5209.3 2134.44  5239.4 2136.43  5260.4 2138.55  5266.4 2139.48
  5275.4 2139.74  5302.5 2141.53  5353.5 2143.89  5358.0 2144.52  5361.0 2144.52
#Mann=3,-1,0
  4842.4    0.07       0  4987.9    0.05       0  4991.9    0.07       0
Bank Sta=4987.9,4991.9
Exp/Cntr=0.3,0.1

Type RM Length L Ch R = 1,1001,456,456,456
BEGIN DESCRIPTION:
Stream0360 2.0
END DESCRIPTION:
XS GIS Cut Line= 3
      1834518.73     13994303.56      1834175.00     13994475.00
      1833975.50     13994723.90
#Sta/Elev= 30
  4615.3 2136.98  4633.0 2136.54  4649.8 2135.33  4677.7 2134.84  4694.5 2133.55
  4716.9 2132.71  4767.2 2131.52  4834.4 2128.05  4873.5 2125.26  4932.4 2122.80
  4956.2 2122.60  4977.1 2120.59  4985.4 2120.29  4989.0 2119.60  4989.3 2119.10
  4992.8 2119.10  4993.0 2119.60  4996.6 2123.75  5002.6 2123.75  5006.6 2126.33
  5013.0 2128.36  5027.4 2129.53  5070.6 2130.62  5090.4 2131.71  5100.6 2132.20
  5127.6 2133.20  5213.3 2138.69  5265.0 2140.95  5291.5 2142.53  5318.4 2143.02
#Mann=8,-1,0
  4615.3    0.07       0  4956.2   0.035       0  4989.0   0.035       0
  4993.0   0.035       0  5090.4    0.07       0  5100.6   0.035       0
  5213.3    0.07       0  5265.0   0.035       0
Bank Sta=4989,4993
Exp/Cntr=0.3,0.1

Type RM Length L Ch R = 1,545,281,281,281
BEGIN DESCRIPTION:
Stream0360 1.0
END DESCRIPTION:
XS GIS Cut Line= 3
      1834074.99     13993975.01      1834025.00     13994075.00
      1833875.02     13994324.97
#Sta/Elev= 30
  4884.3 2127.80  4898.3 2127.84  4915.0 2126.60  4943.0 2125.06  4959.8 2123.84
  4965.3 2123.02  4993.3 2121.13  4999.0 2121.13  5003.9 2120.58  5019.4 2115.85
  5023.2 2115.25  5023.5 2114.75  5027.0 2114.75  5027.2 2115.25  5031.1 2116.19
  5040.8 2116.81  5046.6 2116.70  5062.2 2117.91  5089.4 2117.83  5120.5 2121.39
  5126.3 2120.99  5136.0 2121.69  5163.2 2122.44  5171.0 2123.11  5178.8 2124.32
  5184.6 2123.94  5206.0 2125.41  5252.7 2127.51  5264.3 2128.41  5287.6 2128.40
#Mann=3,-1,0
  4884.3    0.07       0  5023.2    0.05       0  5027.2    0.07       0
Bank Sta=5023.2,5027.2
Exp/Cntr=0.3,0.1

Type RM Length L Ch R = 1,264,168,168,168
BEGIN DESCRIPTION:
Stream0360 0.0
END DESCRIPTION:
XS GIS Cut Line= 3
      1833947.46     13993827.89      1833752.28     13994003.80
      1833713.19     13994221.06
#Sta/Elev= 30
  4773.9 2125.62  4794.7 2125.34  4802.2 2124.38  4808.9 2124.36  4844.5 2121.83
  4886.6 2120.08  4922.5 2117.59  4936.7 2117.05  4950.9 2115.81  4957.6 2114.62
  4965.1 2114.07  5007.0 2113.64  5012.4 2113.30  5012.7 2112.80  5016.2 2112.80
  5016.4 2113.30  5021.2 2114.24  5028.6 2114.56  5033.8 2115.30  5039.8 2115.30
  5098.8 2117.42  5119.2 2119.34  5149.6 2120.87  5158.6 2122.05  5163.7 2122.26
  5170.0 2122.97  5200.4 2123.96  5222.4 2125.28  5241.1 2125.48  5257.4 2126.36
#Mann=3,-1,0
  4773.9    0.07       0  5012.4    0.05       0  5016.4    0.07       0
Bank Sta=5012.4,5016.4
Exp/Cntr=0.3,0.1

Type RM Length L Ch R = 1,96,0,0,0
BEGIN DESCRIPTION:
Stream0360 0.1
END DESCRIPTION:
XS GIS Cut Line= 3
      1833865.70     13993713.92      1833620.50     13993911.38
      1833627.01     13994280.10
#Sta/Elev= 30
  4713.8 2119.40  4722.3 2119.16  4743.1 2119.80  4751.1 2119.19  4771.9 2119.20
  4786.3 2118.05  4835.9 2116.82  4850.3 2115.63  4907.3 2114.27  4928.7 2112.89
  4957.4 2112.62  4971.5 2111.45  4984.7 2109.20  4990.6 2108.68  4990.9 2108.18
  4994.4 2108.18  4994.6 2108.68  4999.1 2111.10  5007.0 2110.35  5013.4 2111.18
  5021.4 2110.84  5027.5 2111.41  5092.2 2112.99  5132.3 2115.23  5162.3 2117.93
  5182.3 2118.23  5212.3 2119.62  5262.3 2123.14  5282.3 2123.33  5397.4 2127.28
#Mann=3,-1,0
  4713.8    0.07       0  4990.6    0.05       0  4994.6    0.07       0
Bank Sta=4990.6,4994.6
Exp/Cntr=0.3,0.1

Chan Stop Cuts=-1