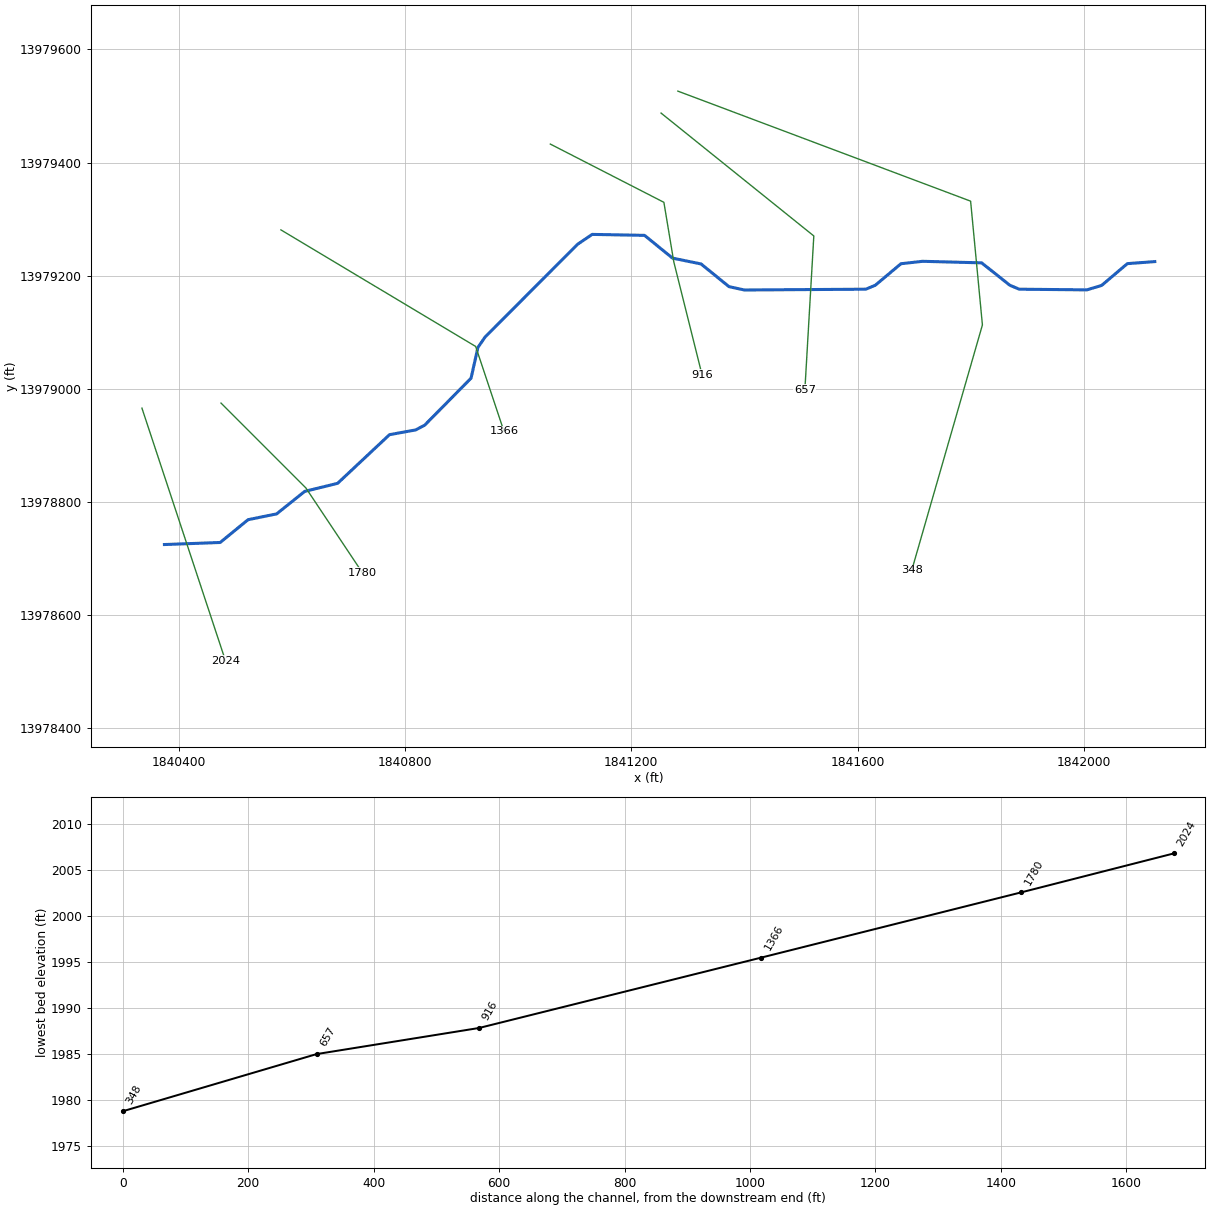
--- Stream0364.prj (project) ---

Proj Title=Stream0364 Base Level Engineering
Current Plan=p01
Default Exp/Contr=0.3,0.1
English Units
Geom File=g01
Flow File=f01
Plan File=p01
Y Axis Title=Elevation
X Axis Title(PF)=Main Channel Distance
X Axis Title(XS)=Station
BEGIN DESCRIPTION:
Stream0364
END DESCRIPTION:
DSS Export Rating Curves= 0
DSS Export Rating Curve Sorted= 0
DSS Export Volume Flow Curves= 0
DXF OffsetX= 0
DXF OffsetY= 0
DXF ScaleX= 1
DXF ScaleY= 10

--- Stream0364.p01 (plan) ---

Plan Title=Multiple Run
Short Identifier=Multiple
Geom File=g01
Flow File=f01
Subcritical Flow
K Sum by GR= 0
Std Step Tol= 0.01
Critical Tol= 0.01
Num of Std Step Trials= 20
Max Error Tol= 0.3
Flow Tol Ratio= 0.001
Split Flow NTrial= 30
Split Flow Tol= 0.02
Split Flow Ratio= 0.02
Log Output Level= 0
Friction Slope Method= 1
Unsteady Friction Slope Method= 2
Unsteady Bridges Friction Slope Method= 1
Parabolic Critical Depth
Global Vel Dist=  1 , 1 , 1
Global Log Level= 0
CheckData=True
Encroach Param= -1, 0, 0, 0
BEGIN DESCRIPTION:
Multiple Run
END DESCRIPTION:

--- Stream0364.f01 (steady flow) ---

Flow Title=Multiple
Number of Profiles=7
Profile Names=10-year,25-year,50-year,1pct_min,100-year,1pct_plu,500-year
River Rch & RM= Stream0364,Reach-1,2024
     815    1369    1886    1257    2509    5006    4385
Boundary for River Rch & Prof#=Stream0364,Reach-1,1
Up Type=0
Dn Type=3
Dn Slope=0.005
Boundary for River Rch & Prof#=Stream0364,Reach-1,2
Up Type=0
Dn Type=3
Dn Slope=0.005
Boundary for River Rch & Prof#=Stream0364,Reach-1,3
Up Type=0
Dn Type=3
Dn Slope=0.005
Boundary for River Rch & Prof#=Stream0364,Reach-1,4
Up Type=0
Dn Type=3
Dn Slope=0.005
Boundary for River Rch & Prof#=Stream0364,Reach-1,5
Up Type=0
Dn Type=3
Dn Slope=0.005
Boundary for River Rch & Prof#=Stream0364,Reach-1,6
Up Type=0
Dn Type=3
Dn Slope=0.005
Boundary for River Rch & Prof#=Stream0364,Reach-1,7
Up Type=0
Dn Type=3
Dn Slope=0.005

--- Stream0364.g01 (geometry) ---

Geom Title=Existing Conditions
Program Version=4.10

River Reach=Stream0364      ,Reach-1
Reach XY= 30
        1840375.       13978725.       1840473.5     13978728.63
      1840522.81     13978768.91      1840573.28     13978779.16
      1840622.81      13978818.9      1840681.05     13978833.16
      1840772.72     13978919.13      1840818.96     13978927.53
       1840834.7     13978935.77      1840916.85     13979018.93
      1840928.98     13979073.35      1840941.65     13979091.67
      1841104.84     13979255.42      1841130.89     13979273.04
      1841223.41     13979271.33      1841272.82     13979231.12
      1841323.26     13979220.81      1841372.65     13979180.71
      1841399.91     13979174.79       1841614.5     13979176.22
      1841631.06     13979183.14      1841676.57     13979221.23
      1841714.83      13979225.5      1841819.06     13979222.75
      1841868.95     13979183.14      1841885.51     13979176.21
      1842004.98       13979175.      1842031.16     13979182.89
      1842076.51     13979221.35        1842125.       13979225.

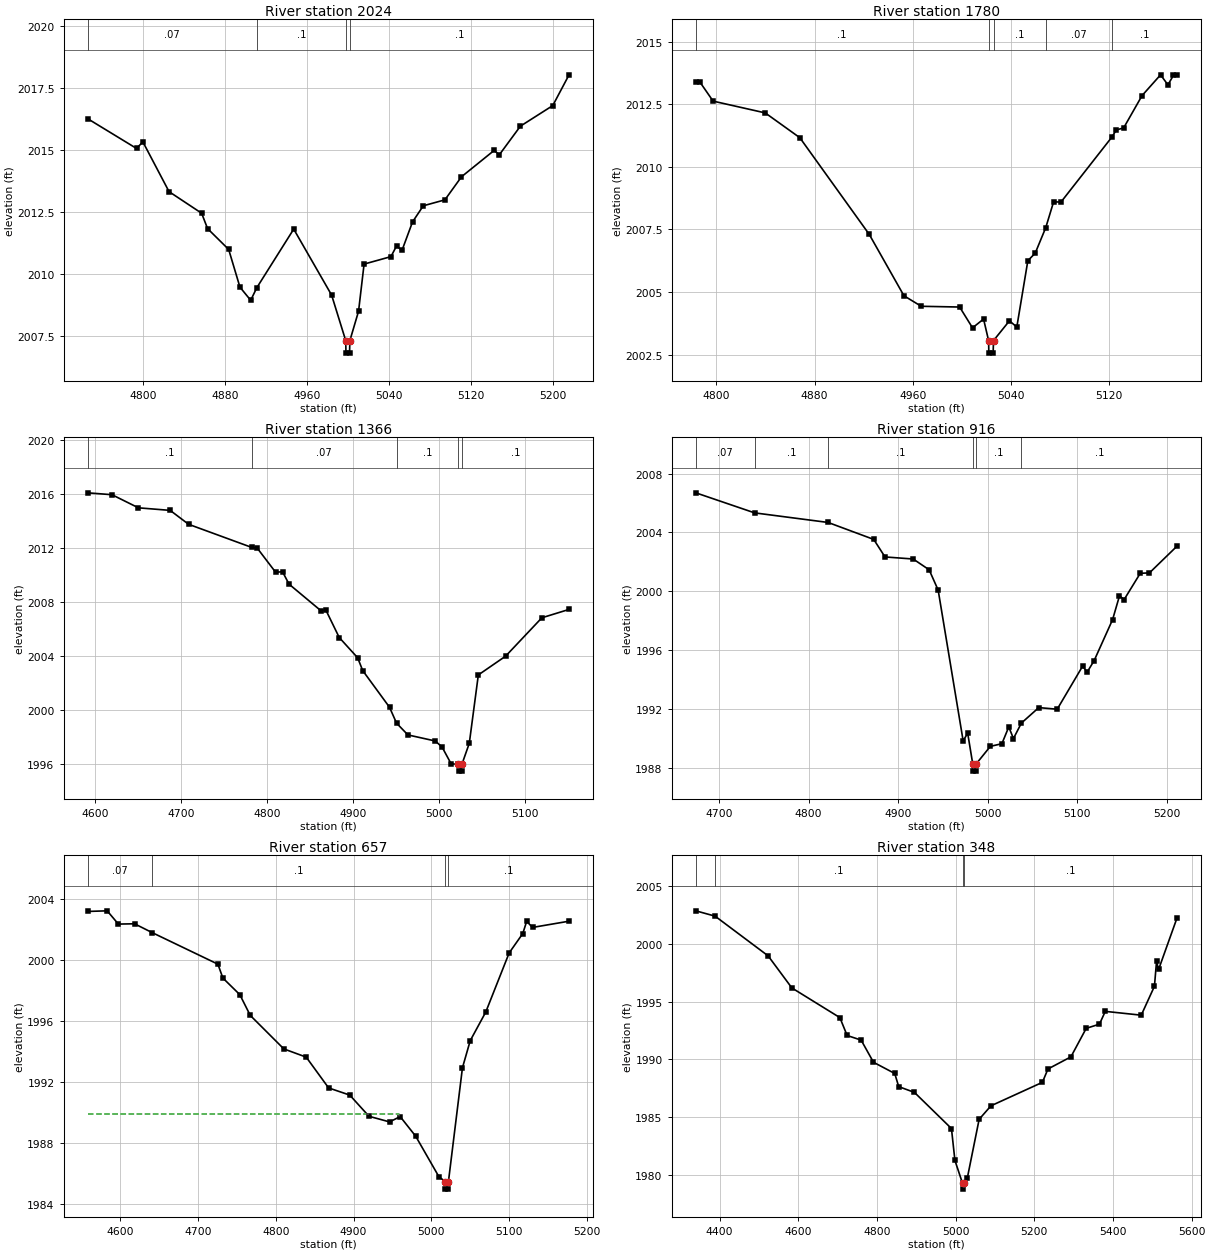
Type RM Length L Ch R = 1 ,2024    ,244,244,244
BEGIN DESCRIPTION:
Stream0364 4.0
END DESCRIPTION:
XS GIS Cut Line= 2
      1840335.26     13978966.04      1840482.81     13978519.91
#Sta/Elev= 30
  4745.6 2016.26  4793.3 2015.06  4799.4 2015.33    4825 2013.32  4856.8 2012.45
  4862.6 2011.83  4883.2 2010.99  4894.2 2009.47  4904.7 2008.94  4910.7 2009.45
  4946.7 2011.81  4983.7 2009.15  4997.5 2007.31  4997.7 2006.81  5001.2 2006.81
  5001.5 2007.31    5010  2008.5  5015.4  2010.4  5041.6  2010.7  5047.1 2011.13
  5052.4 2010.95  5062.7  2012.1  5073.2 2012.75  5094.3 2012.99  5110.5 2013.92
  5142.3 2014.98  5147.5 2014.81    5168 2015.96  5199.6 2016.79  5215.5 2018.03
#Mann= 4 ,-1 , 0
  4745.6     .07       0  4910.7      .1       0  4997.5     .05       0
  5001.5      .1       0
Bank Sta=4997.5,5001.5
XS Rating Curve= 0 ,0
Exp/Cntr=0.3,0.1

Type RM Length L Ch R = 1 ,1780    ,414,414,414
BEGIN DESCRIPTION:
Stream0364 3.0
END DESCRIPTION:
XS GIS Cut Line= 3
      1840475.01     13978974.99        1840625.       13978825.
        1840725.     13978674.99
#Sta/Elev= 30
  4783.2 2013.37  4786.7 2013.37  4797.3 2012.62  4839.8 2012.15    4868 2011.16
  4924.6  2007.3  4952.9 2004.85    4967 2004.43  4998.3  2004.4  5008.8 2003.57
  5017.8 2003.92  5021.9 2003.06  5022.1 2002.56  5025.6 2002.56  5025.9 2003.06
  5038.9 2003.85  5044.9  2003.6  5053.9 2006.25  5059.9 2006.55  5068.5 2007.57
  5074.9  2008.6  5080.9 2008.59  5122.5 2011.19    5126 2011.47    5132 2011.55
    5147 2012.84  5162.1 2013.67  5168.1 2013.27  5172.6 2013.65  5175.6 2013.65
#Mann= 5 ,-1 , 0
  4783.2      .1       0  5021.9     .05       0  5025.9      .1       0
  5068.5     .07       0  5122.5      .1       0
Bank Sta=5021.9,5025.9
XS Rating Curve= 0 ,0
Exp/Cntr=0.3,0.1

Type RM Length L Ch R = 1 ,1366    ,450,450,450
BEGIN DESCRIPTION:
Stream0364 2.0
END DESCRIPTION:
XS GIS Cut Line= 3
      1840580.83     13979281.03        1840925.       13979075.
      1840974.99     13978925.04
#Sta/Elev= 30
  4591.5 2016.07  4619.7 2015.93  4650.4 2014.96  4687.3 2014.77  4708.7 2013.74
    4782 2012.03  4788.4 2011.98  4809.8 2010.19  4817.8 2010.23  4825.4 2009.31
  4862.3 2007.35  4868.2 2007.39  4883.7 2005.36  4905.1 2003.86    4911 2002.91
  4942.1  2000.2  4950.3 1999.02  4963.5 1998.15  4995.3  1997.7  5003.2 1997.25
  5013.7 1996.01  5022.2 1995.97  5022.5 1995.47    5026 1995.47  5026.2 1995.97
  5034.8 1997.53  5045.3 2002.59    5077 2003.98  5119.1 2006.82  5150.7 2007.44
#Mann= 5 ,-1 , 0
  4591.5      .1       0    4782     .07       0  4950.3      .1       0
  5022.2     .05       0  5026.2      .1       0
Bank Sta=5022.2,5026.2
XS Rating Curve= 0 ,0
Exp/Cntr=0.3,0.1

Type RM Length L Ch R = 1 ,916     ,259,259,259
BEGIN DESCRIPTION:
Stream0364 1.0
END DESCRIPTION:
XS GIS Cut Line= 4
      1841056.93     13979432.64      1841257.58     13979329.74
        1841275.       13979225.      1841324.99     13979025.03
#Sta/Elev= 30
  4673.9 2006.69  4739.6 2005.33  4821.7 2004.68  4872.7 2003.53  4885.3 2002.34
  4916.8  2002.2  4934.6 2001.47  4944.7 2000.09  4972.6 1989.87  4977.7 1990.38
  4983.3 1988.31  4983.5 1987.81    4987 1987.81  4987.3 1988.31    5003 1989.49
  5015.9 1989.67  5023.6 1990.81  5028.8 1990.02  5037.7 1991.07  5057.1 1992.12
  5077.7 1992.01  5106.1 1994.93  5111.2 1994.53    5119 1995.31  5139.6 1998.09
  5147.3  1999.7  5152.5 1999.45  5170.5 2001.23  5180.8 2001.26  5211.7 2003.08
#Mann= 6 ,-1 , 0
  4673.9     .07       0  4739.6      .1       0  4821.7      .1       0
  4983.3     .05       0  4987.3      .1       0  5037.7      .1       0
Bank Sta=4983.3,4987.3
XS Rating Curve= 0 ,0
Exp/Cntr=0.3,0.1

Type RM Length L Ch R = 1 ,657     ,309,309,309
BEGIN DESCRIPTION:
Stream0364 0.0
END DESCRIPTION:
XS GIS Cut Line= 3
      1841252.62     13979487.39      1841522.51     13979270.29
      1841506.69     13978998.12
#Sta/Elev= 30
  4558.1 2003.19  4583.1 2003.23  4597.5 2002.36  4618.3 2002.38    4641  2001.8
  4725.5 1999.73  4731.9 1998.82  4753.7 1997.73  4767.1 1996.37  4810.3 1994.17
  4839.1 1993.63  4867.9 1991.61  4895.1 1991.14  4919.8 1989.75  4946.3 1989.38
  4959.9 1989.73  4979.9 1988.44  5009.9 1985.77    5018 1985.47  5018.2 1984.97
  5021.7 1984.97    5022 1985.47    5040 1992.93    5050 1994.71    5070 1996.59
  5100.1 2000.47  5117.6 2001.74  5122.6 2002.54  5130.1 2002.14  5177.1 2002.55
#Mann= 4 ,-1 , 0
  4558.1     .07       0    4641      .1       0    5018     .05       0
    5022      .1       0
#XS Ineff= 2 , 0
         4958.04 1989.88
Permanent Ineff=
       F       F
Bank Sta=5018,5022
XS Rating Curve= 0 ,0
Exp/Cntr=0.3,0.1

Type RM Length L Ch R = 1 ,348     ,0,0,0
BEGIN DESCRIPTION:
Stream0364 0.1
END DESCRIPTION:
XS GIS Cut Line= 4
      1841282.21     13979526.24      1841799.59     13979331.79
      1841820.43     13979113.04      1841695.57     13978679.51
#Sta/Elev= 30
  4339.5 2002.86  4388.5  2002.4  4523.3 1998.96  4583.7 1996.18  4705.7 1993.61
  4724.2 1992.06  4759.8 1991.66  4791.2 1989.74  4845.2 1988.77  4855.3 1987.63
  4895.3 1987.13  4989.4    1984  4998.2 1981.24  5017.6 1979.25  5017.8 1978.75
  5021.6 1979.25  5029.6 1979.69  5059.8  1984.8  5089.9 1985.97  5220.5    1988
  5234.8 1989.16  5293.1 1990.21    5332 1992.68  5365.6 1993.04  5380.5 1994.15
  5471.9 1993.82  5505.4 1996.32  5510.8 1998.48    5516 1997.78  5563.1 2002.27
#Mann= 4 ,-1 , 0
  4339.5     .07       0  4388.5      .1       0  5017.6     .05       0
  5021.6      .1       0
Bank Sta=5017.6,5021.6
XS Rating Curve= 0 ,0
Exp/Cntr=0.3,0.1

Chan Stop Cuts=-1
Use User Specified Reach Order=0
Composite Channel Slope=5