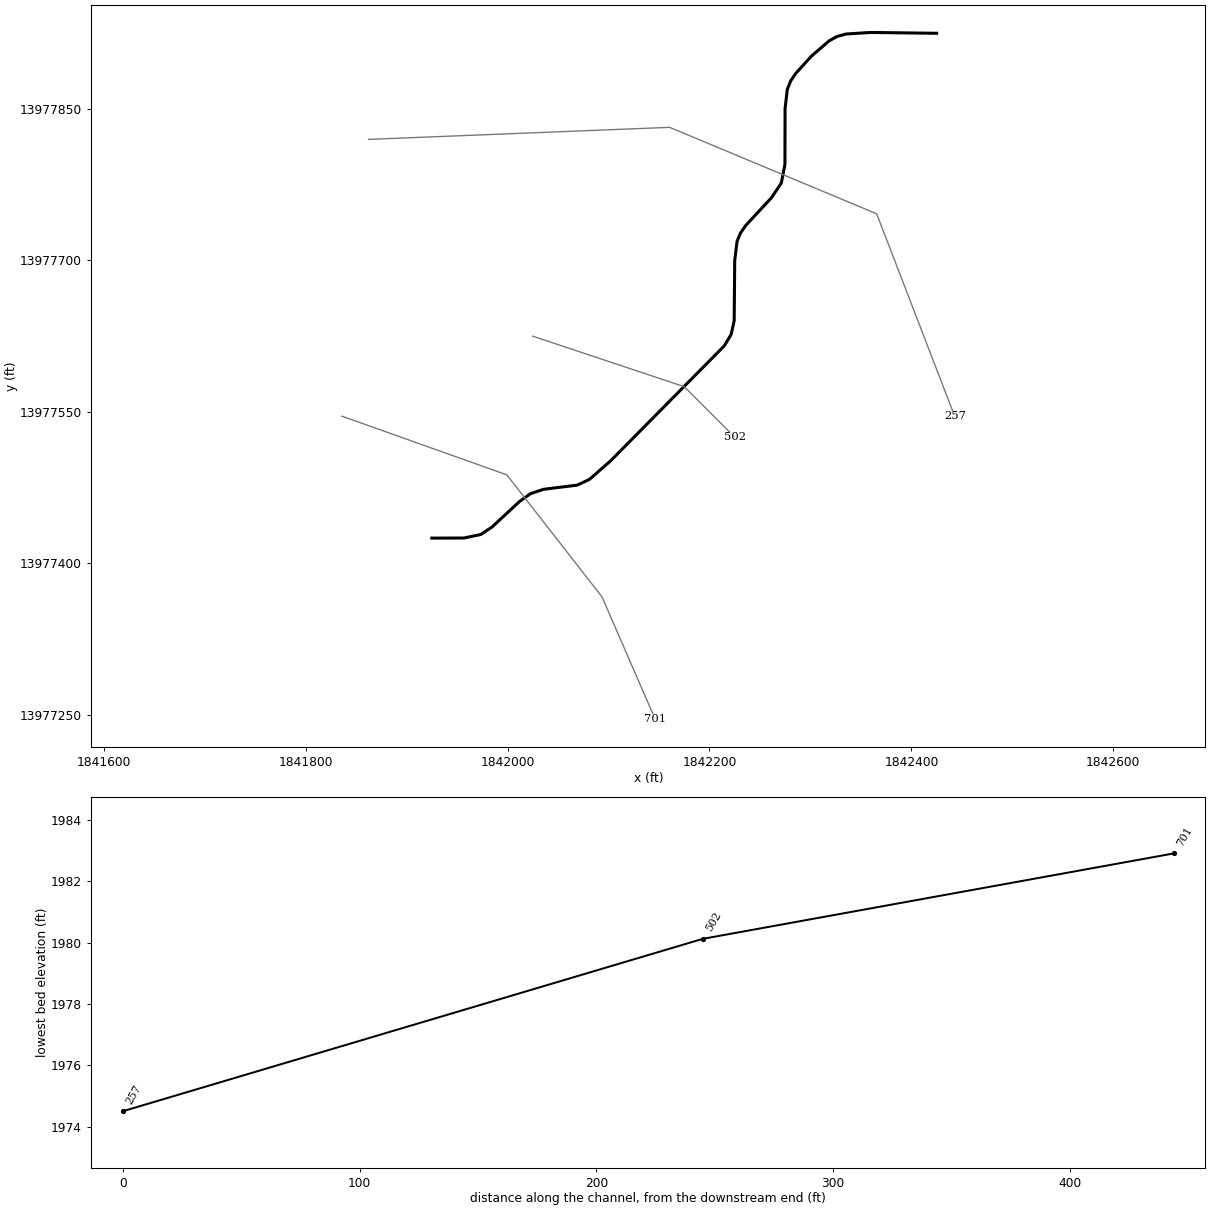
--- Stream0365.prj (project) ---

Proj Title=Stream0365 Base Level Engineering
Current Plan=p01
Default Exp/Contr=0.3,0.1
English Units
Geom File=g01
Flow File=f01
Plan File=p01
BEGIN DESCRIPTION:
Stream0365
END DESCRIPTION:

--- Stream0365.p01 (plan) ---

Plan Title=Multiple Run
Short Identifier=Multiple
Geom File=g01
Flow File=f01
Subcritical Flow
K Sum by GR= 0
Std Step Tol= 0.01
Critical Tol= 0.01
Num of Std Step Trials= 20
Max Error Tol= 0.3
Flow Tol Ratio= 0.001
Split Flow NTrial= 30
Split Flow Tol= 0.02
Split Flow Ratio= 0.02
Log Output Level= 0
Friction Slope Method= 1
Unsteady Friction Slope Method= 2
Unsteady Bridges Friction Slope Method= 1
Parabolic Critical Depth
Global Vel Dist=  1 , 1 , 1
Global Log Level= 0
CheckData=True
Encroach Param= -1, 0, 0, 0
BEGIN DESCRIPTION:
Multiple Run
END DESCRIPTION:

--- Stream0365.f01 (steady flow) ---

Flow Title=Multiple
Number of Profiles=7
Profile Names=10-year,25-year,50-year,1pct_min,100-year,1pct_plu,500-year
River Rch & RM= Stream0365,Reach-1,701
     488     796    1076     706    1409    2810    2379
Boundary for River Rch & Prof#=Stream0365,Reach-1,1
Up Type=0
Dn Type=3
Dn Slope=0.005
Boundary for River Rch & Prof#=Stream0365,Reach-1,2
Up Type=0
Dn Type=3
Dn Slope=0.005
Boundary for River Rch & Prof#=Stream0365,Reach-1,3
Up Type=0
Dn Type=3
Dn Slope=0.005
Boundary for River Rch & Prof#=Stream0365,Reach-1,4
Up Type=0
Dn Type=3
Dn Slope=0.005
Boundary for River Rch & Prof#=Stream0365,Reach-1,5
Up Type=0
Dn Type=3
Dn Slope=0.005
Boundary for River Rch & Prof#=Stream0365,Reach-1,6
Up Type=0
Dn Type=3
Dn Slope=0.005
Boundary for River Rch & Prof#=Stream0365,Reach-1,7
Up Type=0
Dn Type=3
Dn Slope=0.005

--- Stream0365.g01 (geometry) ---

Geom Title=Existing Conditions

River Reach=Stream0365,Reach-1
Reach XY= 30
      1841925.00     13977425.00      1841956.81     13977425.10
      1841973.51     13977428.60      1841984.60     13977435.98
      1842011.85     13977461.22      1842022.76     13977469.03
      1842035.69     13977473.34      1842068.98     13977477.47
      1842081.06     13977483.13      1842101.83     13977501.29
      1842214.48     13977615.21      1842221.39     13977626.50
      1842224.48     13977640.22      1842225.01     13977700.00
      1842227.36     13977719.02      1842230.81     13977727.31
      1842235.89     13977734.63      1842261.18     13977761.87
      1842271.14     13977776.60      1842274.75     13977795.11
      1842274.87     13977850.13      1842277.06     13977869.31
      1842280.39     13977877.71      1842285.34     13977885.16
      1842300.95     13977902.34      1842318.41     13977917.42
      1842326.12     13977921.74      1842335.13     13977924.27
      1842359.59     13977925.83      1842425.00     13977925.00

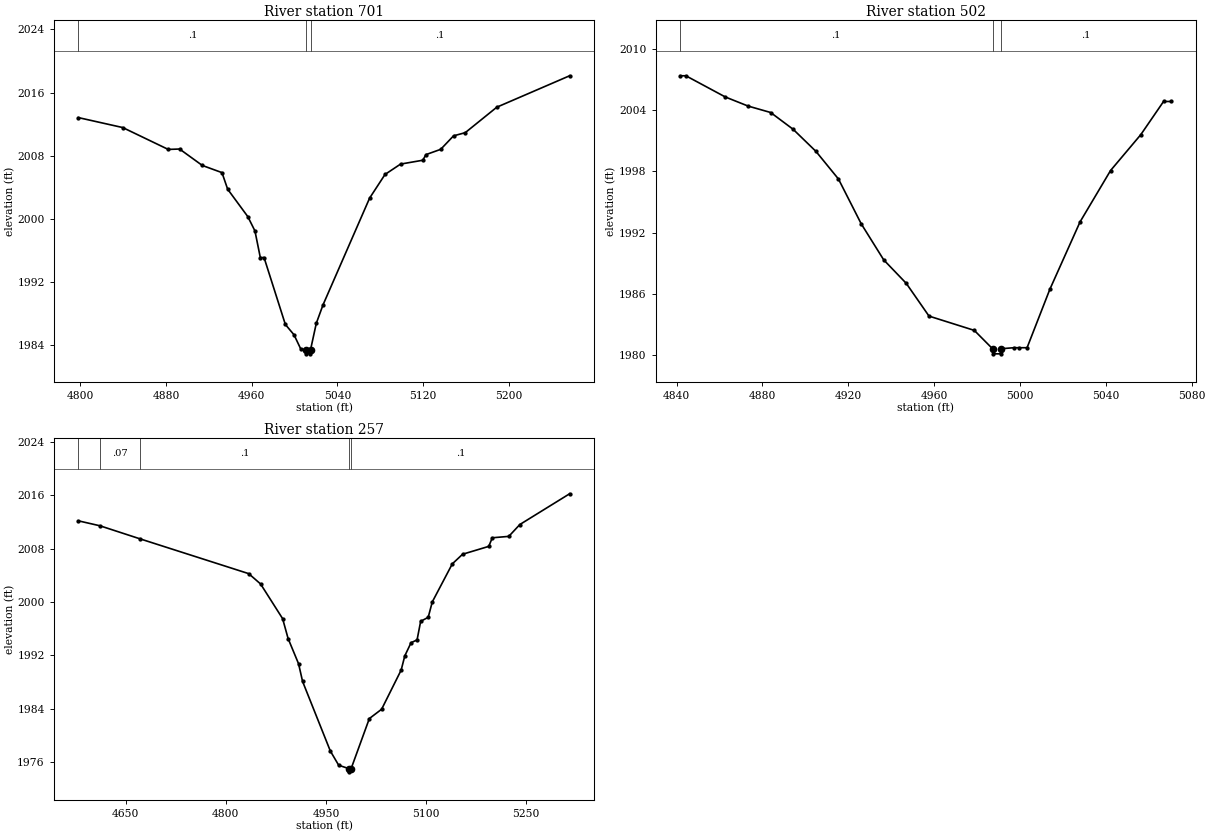
Type RM Length L Ch R = 1,701,199,199,199
BEGIN DESCRIPTION:
Stream0365 2.0
END DESCRIPTION:
XS GIS Cut Line= 4
      1841835.98     13977545.78      1841999.32     13977487.65
      1842093.59     13977366.75      1842146.25     13977245.58
#Sta/Elev= 30
  4798.1 2012.83  4839.5 2011.57  4882.0 2008.80  4892.6 2008.85  4913.8 2006.77
  4932.2 2005.86  4937.5 2003.76  4956.3 2000.29  4963.0 1998.47  4968.0 1995.10
  4971.5 1995.10  4991.4 1986.62  4999.5 1985.31  5005.8 1983.51  5010.9 1983.40
  5011.1 1982.90  5014.6 1982.90  5014.9 1983.40  5020.3 1986.77  5026.6 1989.11
  5070.1 2002.63  5084.5 2005.63  5099.0 2006.94  5119.8 2007.43  5122.7 2008.14
  5136.5 2008.81  5148.5 2010.52  5159.4 2010.92  5188.9 2014.15  5256.9 2018.13
#Mann=3,-1,0
  4798.1     0.1       0  5010.9    0.05       0  5014.9     0.1       0
Bank Sta=5010.9,5014.9
Exp/Cntr=0.3,0.1

Type RM Length L Ch R = 1,502,245,245,245
BEGIN DESCRIPTION:
Stream0365 1.0
END DESCRIPTION:
XS GIS Cut Line= 3
      1842024.97     13977625.01      1842175.00     13977575.00
      1842225.03     13977524.97
#Sta/Elev= 26
  4841.6 2007.38  4844.3 2007.38  4862.7 2005.30  4873.3 2004.41  4883.8 2003.78
  4894.3 2002.13  4904.9 1999.97  4915.4 1997.26  4926.0 1992.87  4936.5 1989.33
  4947.0 1987.03  4957.6 1983.82  4978.7 1982.42  4987.2 1980.62  4987.5 1980.12
  4991.0 1980.12  4991.2 1980.62  4997.1 1980.72  4999.7 1980.72  5003.3 1980.72
  5013.9 1986.44  5028.0 1993.06  5042.2 1998.09  5056.3 2001.61  5066.9 2004.86
  5070.5 2004.86
#Mann=3,-1,0
  4841.6     0.1       0  4987.2    0.05       0  4991.2     0.1       0
Bank Sta=4987.2,4991.2
Exp/Cntr=0.3,0.1

Type RM Length L Ch R = 1,257,0,0,0
BEGIN DESCRIPTION:
Stream0365 0.0
END DESCRIPTION:
XS GIS Cut Line= 4
      1841862.36     13977819.91      1842160.56     13977831.85
      1842365.63     13977746.19      1842442.96     13977545.45
#Sta/Elev= 30
  4579.2 2012.16  4611.4 2011.42  4671.8 2009.45  4834.3 2004.24  4852.1 2002.69
  4885.1 1997.49  4893.3 1994.51  4909.0 1990.72  4915.0 1988.07  4956.6 1977.63
  4969.1 1975.50  4983.8 1975.01  4984.1 1974.51  4987.8 1975.01  5015.0 1982.50
  5033.4 1983.90  5062.7 1989.78  5068.1 1991.90  5077.5 1993.88  5086.5 1994.30
  5091.9 1997.09  5103.2 1997.69  5109.3 2000.00  5139.3 2005.71  5154.7 2007.15
  5193.9 2008.33  5199.2 2009.62  5223.9 2009.83  5240.5 2011.61  5315.0 2016.22
#Mann=5,-1,0
  4579.2     0.1       0  4611.4    0.07       0  4671.8     0.1       0
  4983.8    0.05       0  4987.8     0.1       0
Bank Sta=4983.8,4987.8
Exp/Cntr=0.3,0.1

Chan Stop Cuts=-1