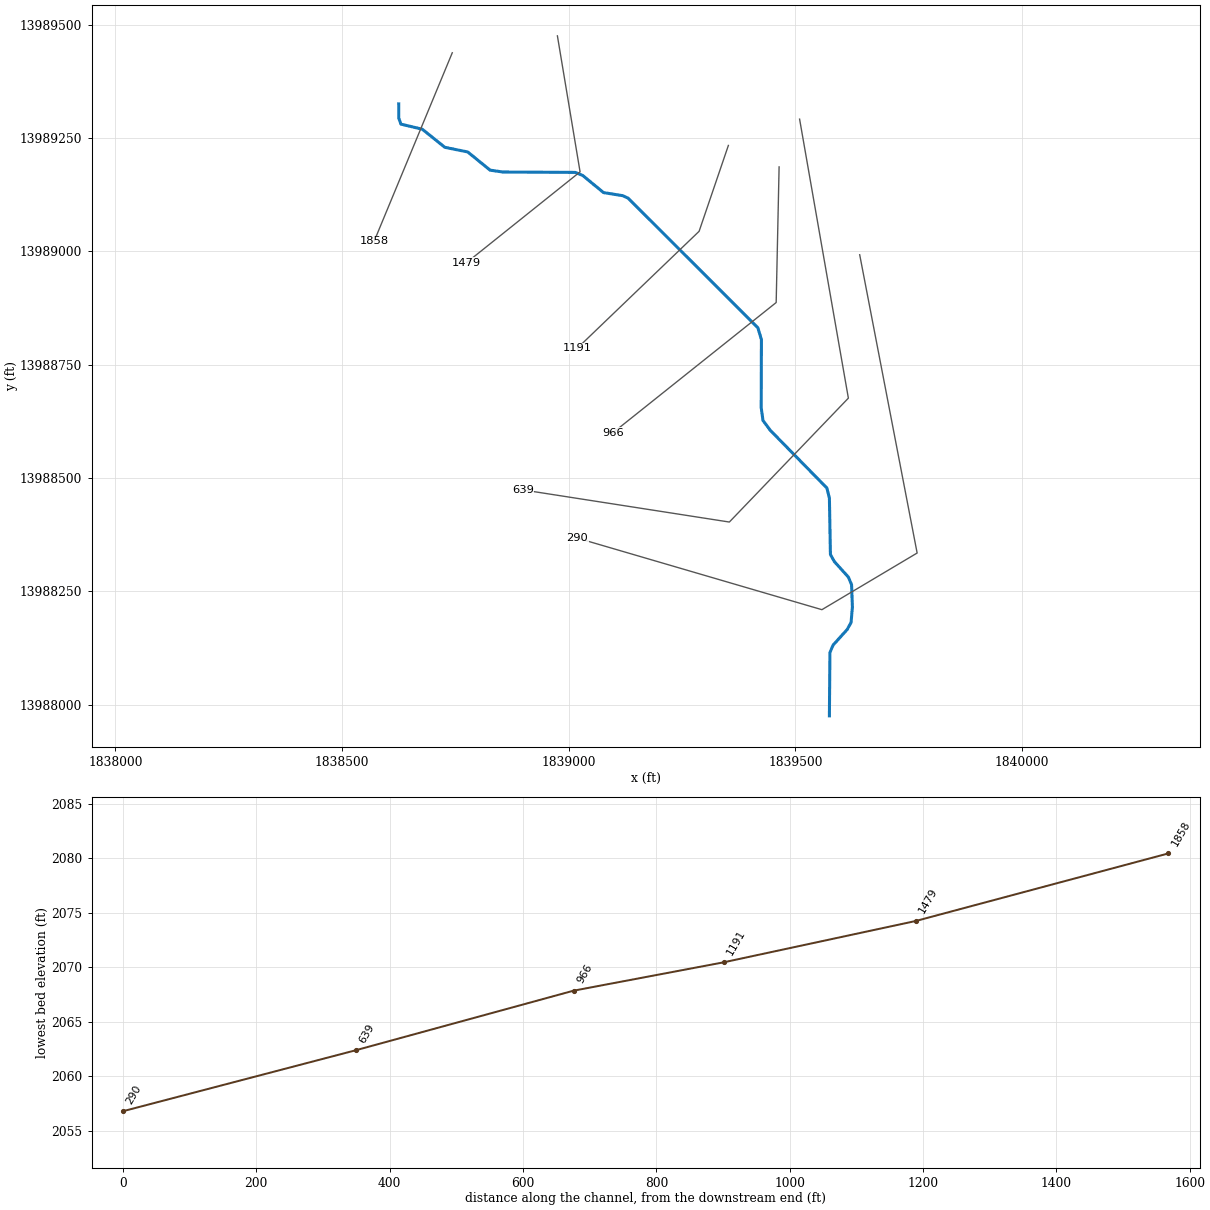
--- Stream0368.prj (project) ---

Proj Title=Stream0368 Base Level Engineering
Current Plan=p01
Default Exp/Contr=0.3,0.1
English Units
Geom File=g01
Flow File=f01
Plan File=p01
BEGIN DESCRIPTION:
Stream0368
END DESCRIPTION:

--- Stream0368.p01 (plan) ---

Plan Title=Multiple Run
Short Identifier=Multiple
Geom File=g01
Flow File=f01
Subcritical Flow
K Sum by GR= 0
Std Step Tol= 0.01
Critical Tol= 0.01
Num of Std Step Trials= 20
Max Error Tol= 0.3
Flow Tol Ratio= 0.001
Split Flow NTrial= 30
Split Flow Tol= 0.02
Split Flow Ratio= 0.02
Log Output Level= 0
Friction Slope Method= 1
Unsteady Friction Slope Method= 2
Unsteady Bridges Friction Slope Method= 1
Parabolic Critical Depth
Global Vel Dist=  1 , 1 , 1
Global Log Level= 0
CheckData=True
Encroach Param= -1, 0, 0, 0
BEGIN DESCRIPTION:
Multiple Run
END DESCRIPTION:

--- Stream0368.f01 (steady flow) ---

Flow Title=Multiple
Number of Profiles=7
Profile Names=10-year,25-year,50-year,1pct_min,100-year,1pct_plu,500-year
River Rch & RM= Stream0368,Reach-1,1858
     410     655     874     566    1129    2252    1854
Boundary for River Rch & Prof#=Stream0368,Reach-1,1
Up Type=0
Dn Type=3
Dn Slope=0.005
Boundary for River Rch & Prof#=Stream0368,Reach-1,2
Up Type=0
Dn Type=3
Dn Slope=0.005
Boundary for River Rch & Prof#=Stream0368,Reach-1,3
Up Type=0
Dn Type=3
Dn Slope=0.005
Boundary for River Rch & Prof#=Stream0368,Reach-1,4
Up Type=0
Dn Type=3
Dn Slope=0.005
Boundary for River Rch & Prof#=Stream0368,Reach-1,5
Up Type=0
Dn Type=3
Dn Slope=0.005
Boundary for River Rch & Prof#=Stream0368,Reach-1,6
Up Type=0
Dn Type=3
Dn Slope=0.005
Boundary for River Rch & Prof#=Stream0368,Reach-1,7
Up Type=0
Dn Type=3
Dn Slope=0.005

--- Stream0368.g01 (geometry) ---

Geom Title=Existing Conditions

River Reach=Stream0368,Reach-1
Reach XY= 30
      1838625.00     13989325.00      1838625.06     13989293.44
      1838629.90     13989280.28      1838677.01     13989269.00
      1838726.69     13989229.13      1838777.18     13989218.88
      1838826.55     13989178.75      1838854.85     13989174.64
      1839014.50     13989173.80      1839031.08     13989166.91
      1839076.75     13989129.22      1839118.97     13989122.50
      1839131.06     13989116.86      1839417.19     13988831.19
      1839425.04     13988805.02      1839424.57     13988654.82
      1839428.54     13988626.46      1839444.61     13988604.84
      1839569.53     13988477.45      1839575.02     13988455.01
      1839577.27     13988330.94      1839585.86     13988315.35
      1839616.91     13988281.03      1839623.90     13988264.45
      1839625.77     13988214.95      1839622.83     13988180.97
      1839614.19     13988165.37      1839583.13     13988131.06
      1839576.17     13988114.52      1839575.00     13987975.00

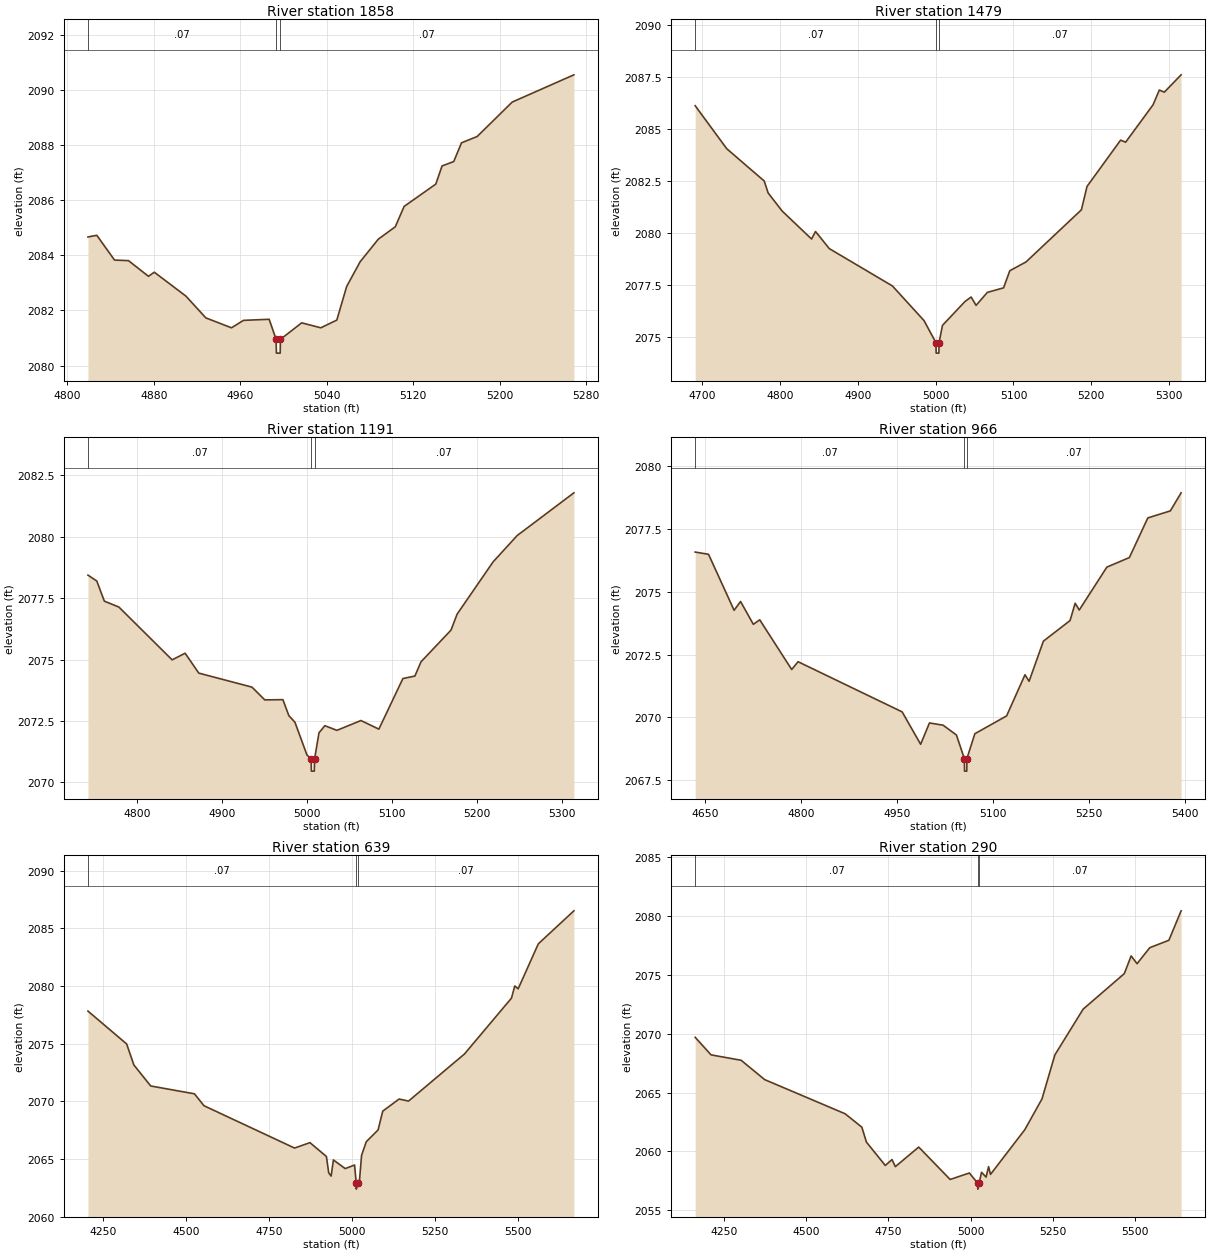
Type RM Length L Ch R = 1,1858,379,379,379
BEGIN DESCRIPTION:
Stream0368 2.0
END DESCRIPTION:
XS GIS Cut Line= 2
      1838743.09     13989437.71      1838570.89     13989022.28
#Sta/Elev= 30
  4819.1 2084.67  4827.3 2084.73  4843.7 2083.83  4856.6 2083.81  4875.1 2083.24
  4880.5 2083.39  4909.8 2082.52  4928.2 2081.73  4951.9 2081.37  4963.0 2081.64
  4986.8 2081.68  4993.2 2080.95  4993.5 2080.45  4997.0 2080.45  4997.2 2080.95
  5016.9 2081.55  5034.6 2081.37  5049.4 2081.65  5058.5 2082.87  5071.0 2083.77
  5087.8 2084.59  5103.5 2085.04  5111.7 2085.78  5141.0 2086.59  5146.8 2087.25
  5157.6 2087.41  5164.8 2088.09  5179.3 2088.32  5211.7 2089.57  5268.8 2090.56
#Mann=3,-1,0
  4819.1    0.07       0  4993.2    0.05       0  4997.2    0.07       0
Bank Sta=4993.2,4997.2
Exp/Cntr=0.3,0.1

Type RM Length L Ch R = 1,1479,288,288,288
BEGIN DESCRIPTION:
Stream0368 1.0
END DESCRIPTION:
XS GIS Cut Line= 3
      1838975.00     13989474.97      1839025.00     13989175.00
      1838774.97     13988974.98
#Sta/Elev= 30
  4691.1 2086.11  4731.6 2084.05  4779.8 2082.50  4784.8 2081.93  4802.6 2081.07
  4840.6 2079.72  4845.7 2080.08  4863.4 2079.26  4944.5 2077.47  4985.1 2075.81
  5000.4 2074.75  5000.7 2074.25  5004.2 2074.25  5004.4 2074.75  5008.8 2075.58
  5037.6 2076.72  5045.6 2076.94  5052.0 2076.54  5066.4 2077.16  5087.3 2077.38
  5095.3 2078.20  5116.1 2078.62  5187.3 2081.12  5194.5 2082.24  5237.7 2084.46
  5244.1 2084.36  5279.3 2086.15  5287.4 2086.86  5293.8 2086.76  5315.4 2087.59
#Mann=3,-1,0
  4691.1    0.07       0  5000.4    0.05       0  5004.4    0.07       0
Bank Sta=5000.4,5004.4
Exp/Cntr=0.3,0.1

Type RM Length L Ch R = 1,1191,225,225,225
BEGIN DESCRIPTION:
Stream0368 0.0
END DESCRIPTION:
XS GIS Cut Line= 3
      1839352.16     13989233.28      1839287.58     13989043.85
      1839019.25     13988786.25
#Sta/Elev= 30
  4742.3 2078.44  4752.7 2078.20  4761.6 2077.38  4778.7 2077.14  4841.4 2074.99
  4856.7 2075.26  4872.8 2074.45  4935.4 2073.88  4950.5 2073.36  4971.8 2073.37
  4978.8 2072.72  4986.0 2072.45  5000.1 2071.12  5005.1 2070.96  5005.3 2070.46
  5008.8 2070.46  5009.1 2070.96  5014.3 2072.02  5021.2 2072.31  5035.4 2072.12
  5063.7 2072.52  5084.8 2072.17  5113.1 2074.23  5127.2 2074.33  5134.4 2074.91
  5169.7 2076.20  5176.9 2076.85  5219.3 2078.98  5247.6 2080.05  5314.4 2081.79
#Mann=3,-1,0
  4742.3    0.07       0  5005.1    0.05       0  5009.1    0.07       0
Bank Sta=5005.1,5009.1
Exp/Cntr=0.3,0.1

Type RM Length L Ch R = 1,966,327,327,327
BEGIN DESCRIPTION:
Stream0368 4.0
END DESCRIPTION:
XS GIS Cut Line= 3
      1839464.06     13989185.93      1839457.60     13988886.74
      1839097.10     13988599.19
#Sta/Elev= 30
  4634.0 2076.59  4654.9 2076.50  4694.9 2074.27  4705.0 2074.62  4725.0 2073.71
  4735.0 2073.89  4785.0 2071.91  4795.0 2072.22  4957.9 2070.22  4986.8 2068.93
  5000.6 2069.78  5022.0 2069.69  5042.8 2069.30  5055.2 2068.36  5055.5 2067.86
  5059.0 2067.86  5059.2 2068.36  5071.6 2069.35  5121.3 2070.06  5150.1 2071.70
  5156.5 2071.44  5178.9 2073.04  5220.6 2073.86  5228.6 2074.55  5235.0 2074.28
  5278.2 2075.99  5313.4 2076.37  5342.3 2077.95  5377.5 2078.23  5394.4 2078.95
#Mann=3,-1,0
  4634.0    0.07       0  5055.2    0.05       0  5059.2    0.07       0
Bank Sta=5055.2,5059.2
Exp/Cntr=0.3,0.1

Type RM Length L Ch R = 1,639,349,349,349
BEGIN DESCRIPTION:
Stream0368 3.0
END DESCRIPTION:
XS GIS Cut Line= 4
      1839509.26     13989291.33      1839616.86     13988675.83
      1839354.30     13988402.50      1838899.03     13988473.37
#Sta/Elev= 30
  4203.5 2077.82  4320.2 2074.97  4341.9 2073.15  4392.7 2071.33  4524.6 2070.65
  4553.1 2069.62  4826.2 2065.95  4872.6 2066.42  4922.2 2065.22  4929.2 2063.80
  4936.4 2063.52  4943.3 2064.92  4978.8 2064.17  5007.1 2064.48  5012.1 2062.89
  5012.3 2062.39  5016.1 2062.89  5021.3 2062.94  5028.2 2065.32  5042.4 2066.50
  5077.9 2067.52  5092.0 2069.15  5141.4 2070.20  5169.7 2070.02  5338.2 2074.10
  5479.9 2078.94  5490.0 2080.00  5500.1 2079.75  5560.9 2083.65  5668.1 2086.51
#Mann=3,-1,0
  4203.5    0.07       0  5012.1    0.05       0  5016.1    0.07       0
Bank Sta=5012.1,5016.1
Exp/Cntr=0.3,0.1

Type RM Length L Ch R = 1,290,0,0,0
BEGIN DESCRIPTION:
Stream0368 0.1
END DESCRIPTION:
XS GIS Cut Line= 4
      1839641.83     13988992.14      1839768.56     13988334.18
      1839558.49     13988209.18      1839019.31     13988366.95
#Sta/Elev= 30
  4163.4 2069.69  4211.6 2068.20  4303.1 2067.74  4374.4 2066.10  4618.8 2063.20
  4669.7 2062.06  4683.7 2060.79  4741.0 2058.81  4761.3 2059.31  4771.5 2058.71
  4842.5 2060.37  4938.0 2057.62  4996.4 2058.17  5021.8 2057.30  5022.0 2056.80
  5025.8 2057.30  5033.4 2058.23  5047.1 2057.82  5054.8 2058.71  5060.6 2058.05
  5164.9 2061.85  5217.0 2064.46  5256.2 2068.20  5342.0 2072.08  5467.1 2075.10
  5487.9 2076.60  5505.8 2075.94  5544.5 2077.30  5602.5 2077.93  5639.7 2080.43
#Mann=3,-1,0
  4163.4    0.07       0  5021.8    0.05       0  5025.8    0.07       0
Bank Sta=5021.8,5025.8
Exp/Cntr=0.3,0.1

Chan Stop Cuts=-1