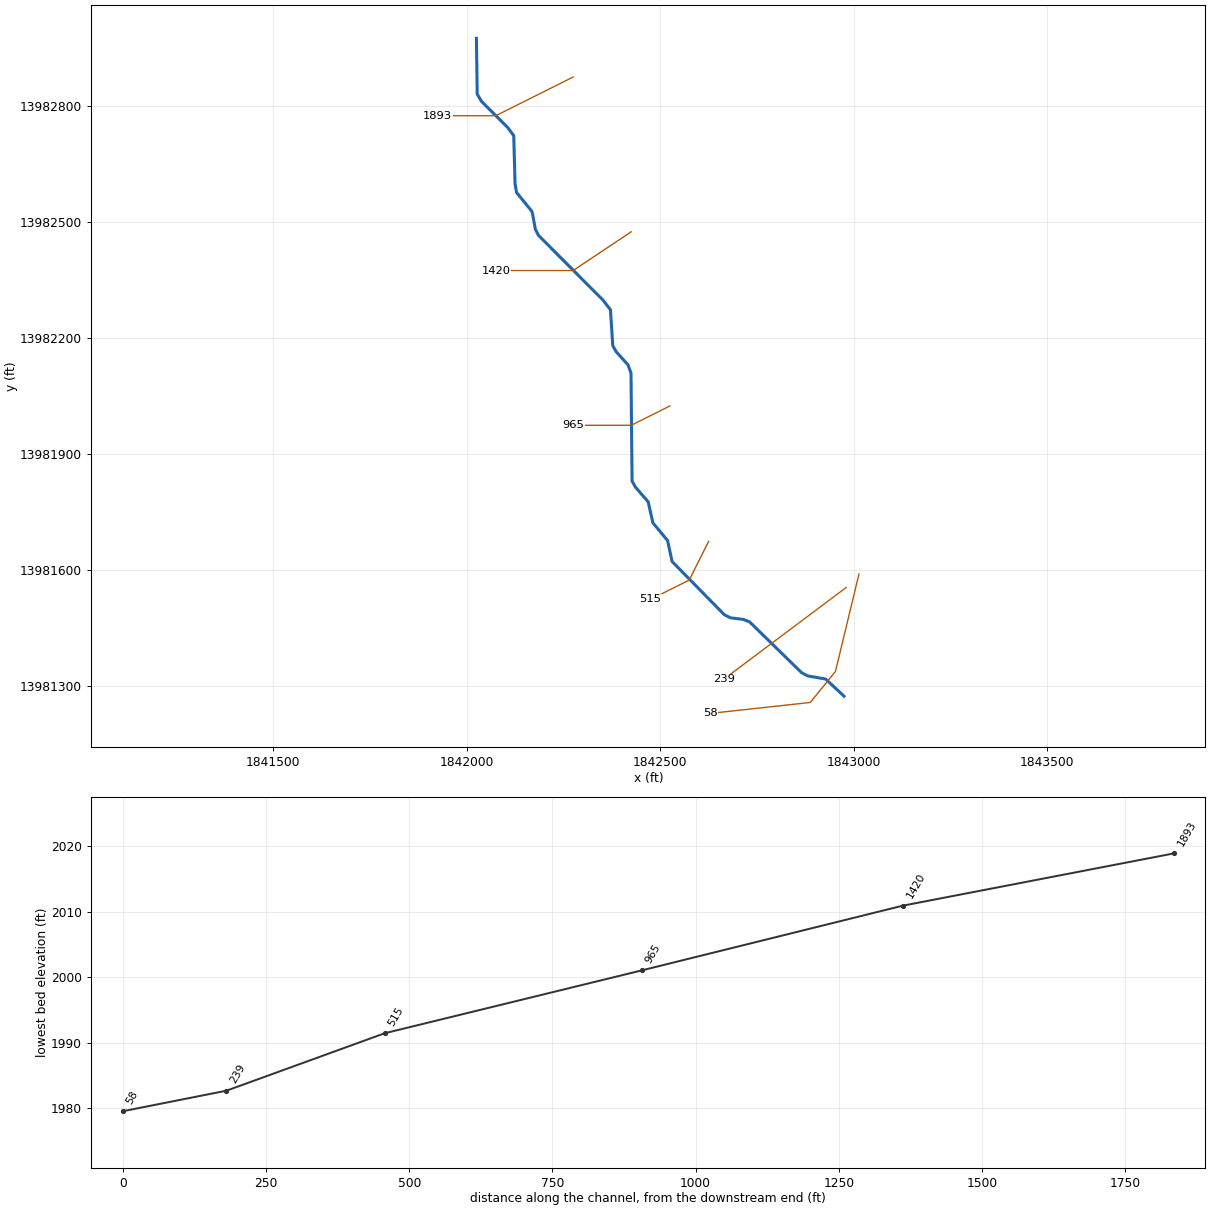
--- Stream0370.prj (project) ---

Proj Title=Stream0370 Base Level Engineering
Current Plan=p01
Default Exp/Contr=0.3,0.1
English Units
Geom File=g01
Flow File=f01
Plan File=p01
BEGIN DESCRIPTION:
Stream0370
END DESCRIPTION:

--- Stream0370.p01 (plan) ---

Plan Title=Multiple Run
Short Identifier=Multiple
Geom File=g01
Flow File=f01
Subcritical Flow
K Sum by GR= 0
Std Step Tol= 0.01
Critical Tol= 0.01
Num of Std Step Trials= 20
Max Error Tol= 0.3
Flow Tol Ratio= 0.001
Split Flow NTrial= 30
Split Flow Tol= 0.02
Split Flow Ratio= 0.02
Log Output Level= 0
Friction Slope Method= 1
Unsteady Friction Slope Method= 2
Unsteady Bridges Friction Slope Method= 1
Parabolic Critical Depth
Global Vel Dist=  1 , 1 , 1
Global Log Level= 0
CheckData=True
Encroach Param= -1, 0, 0, 0
BEGIN DESCRIPTION:
Multiple Run
END DESCRIPTION:

--- Stream0370.f01 (steady flow) ---

Flow Title=Multiple
Number of Profiles=7
Profile Names=10-year,25-year,50-year,1pct_min,100-year,1pct_plu,500-year
River Rch & RM= Stream0370,Reach-1,1893
     577     950    1293     853    1702    3396    2909
Boundary for River Rch & Prof#=Stream0370,Reach-1,1
Up Type=0
Dn Type=3
Dn Slope=0.005
Boundary for River Rch & Prof#=Stream0370,Reach-1,2
Up Type=0
Dn Type=3
Dn Slope=0.005
Boundary for River Rch & Prof#=Stream0370,Reach-1,3
Up Type=0
Dn Type=3
Dn Slope=0.005
Boundary for River Rch & Prof#=Stream0370,Reach-1,4
Up Type=0
Dn Type=3
Dn Slope=0.005
Boundary for River Rch & Prof#=Stream0370,Reach-1,5
Up Type=0
Dn Type=3
Dn Slope=0.005
Boundary for River Rch & Prof#=Stream0370,Reach-1,6
Up Type=0
Dn Type=3
Dn Slope=0.005
Boundary for River Rch & Prof#=Stream0370,Reach-1,7
Up Type=0
Dn Type=3
Dn Slope=0.005

--- Stream0370.g01 (geometry) ---

Geom Title=Existing Conditions

River Reach=Stream0370,Reach-1
Reach XY= 30
      1842025.00     13982975.00      1842027.02     13982830.84
      1842038.39     13982811.69      1842105.35     13982745.14
      1842121.44     13982723.53      1842124.81     13982599.92
      1842128.76     13982576.56      1842168.86     13982527.17
      1842177.50     13982481.03      1842185.76     13982465.32
      1842352.12     13982298.52      1842371.39     13982273.50
      1842377.36     13982180.98      1842385.90     13982165.37
      1842416.86     13982131.06      1842424.48     13982109.78
      1842427.24     13981830.93      1842435.80     13981815.33
      1842468.88     13981777.18      1842481.08     13981722.80
      1842518.90     13981677.19      1842530.83     13981622.70
      1842665.32     13981485.78      1842681.05     13981477.53
      1842714.36     13981473.45      1842731.05     13981466.84
      1842865.29     13981335.70      1842880.97     13981327.34
      1842927.35     13981319.29      1842975.00     13981275.00

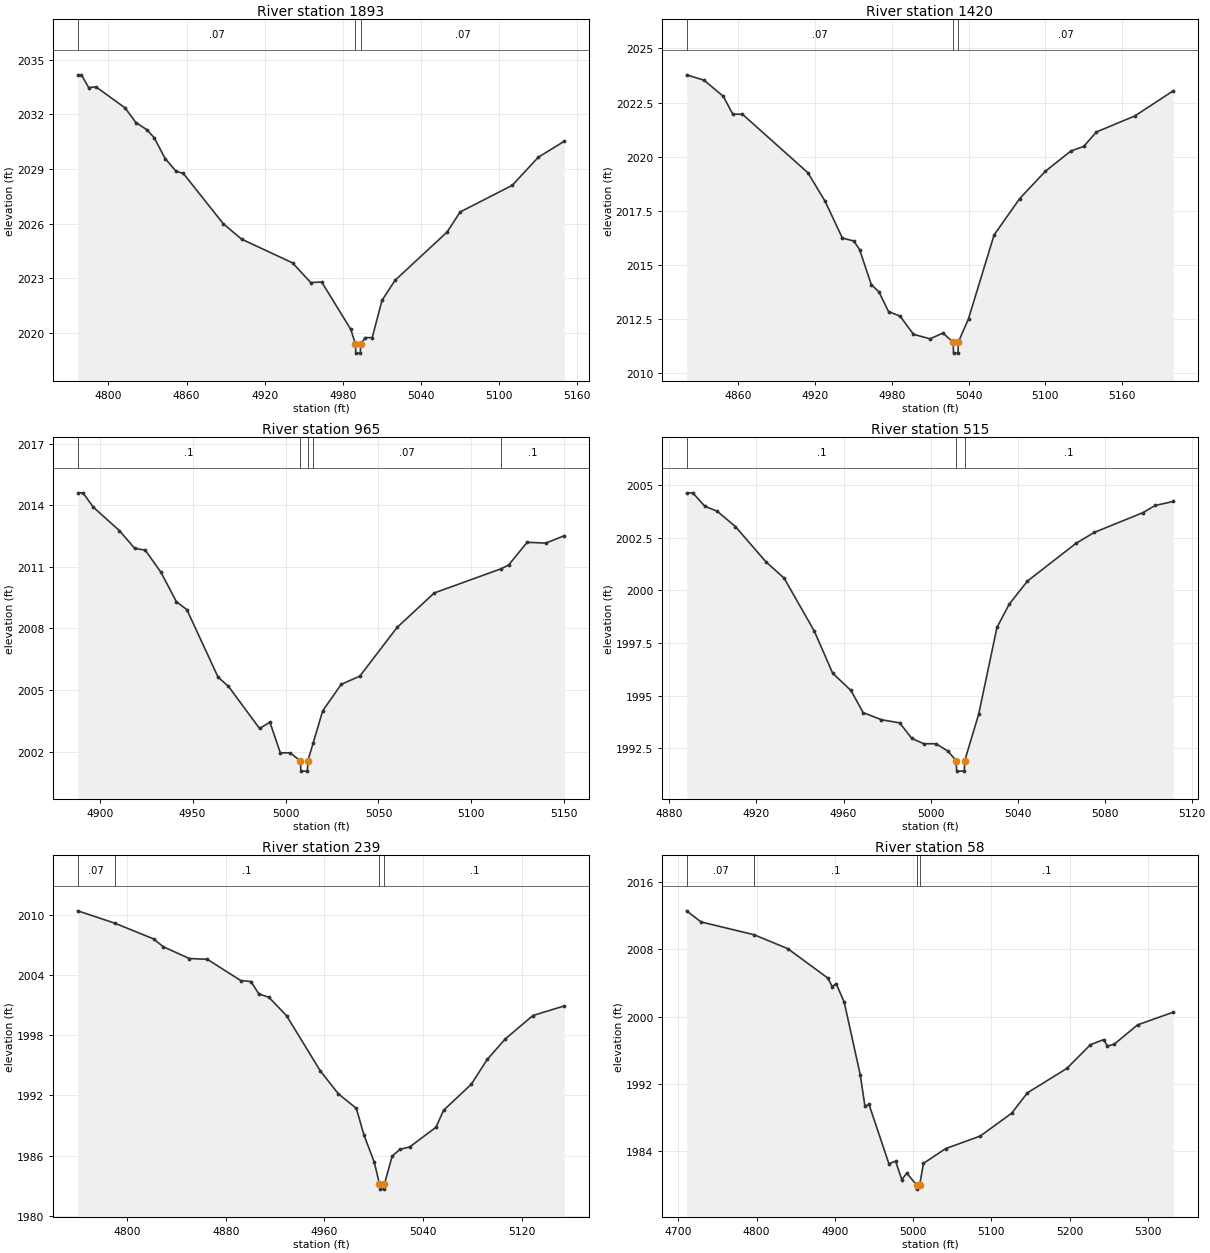
Type RM Length L Ch R = 1,1893,473,473,473
BEGIN DESCRIPTION:
Stream0370 4.0
END DESCRIPTION:
XS GIS Cut Line= 3
      1842274.99     13982874.99      1842075.00     13982775.00
      1841924.99     13982775.00
#Sta/Elev= 30
  4776.4 2034.16  4779.2 2034.16  4784.8 2033.46  4790.4 2033.50  4812.7 2032.35
  4821.1 2031.54  4829.5 2031.15  4835.1 2030.71  4843.5 2029.57  4851.9 2028.87
  4857.4 2028.76  4888.2 2025.99  4902.2 2025.15  4941.3 2023.85  4955.3 2022.77
  4963.7 2022.80  4986.0 2020.21  4989.6 2019.40  4989.9 2018.90  4993.4 2018.90
  4993.6 2019.40  4997.2 2019.75  5002.5 2019.75  5010.0 2021.79  5020.0 2022.89
  5060.0 2025.54  5070.0 2026.64  5110.0 2028.10  5130.0 2029.64  5150.0 2030.52
#Mann=3,-1,0
  4776.4    0.07       0  4989.6    0.05       0  4993.6    0.07       0
Bank Sta=4989.6,4993.6
Exp/Cntr=0.3,0.1

Type RM Length L Ch R = 1,1420,455,455,455
BEGIN DESCRIPTION:
Stream0370 3.0
END DESCRIPTION:
XS GIS Cut Line= 3
      1842425.03     13982475.02      1842275.00     13982375.00
      1842075.01     13982375.00
#Sta/Elev= 30
  4819.7 2023.78  4833.3 2023.53  4848.3 2022.79  4855.8 2021.96  4863.3 2021.96
  4914.4 2019.26  4927.9 2017.94  4941.4 2016.24  4950.4 2016.10  4954.9 2015.70
  4964.0 2014.09  4970.0 2013.75  4977.5 2012.84  4986.5 2012.63  4997.0 2011.79
  5010.0 2011.58  5020.0 2011.85  5028.0 2011.42  5028.3 2010.92  5031.8 2010.92
  5032.0 2011.42  5040.0 2012.51  5060.0 2016.38  5080.0 2018.06  5100.0 2019.32
  5120.0 2020.26  5130.0 2020.47  5140.0 2021.14  5170.0 2021.88  5200.0 2023.04
#Mann=3,-1,0
  4819.7    0.07       0  5028.0    0.05       0  5032.0    0.07       0
Bank Sta=5028,5032
Exp/Cntr=0.3,0.1

Type RM Length L Ch R = 1,965,450,450,450
BEGIN DESCRIPTION:
Stream0370 2.0
END DESCRIPTION:
XS GIS Cut Line= 3
      1842525.00     13982025.00      1842425.00     13981975.00
      1842275.01     13981975.00
#Sta/Elev= 30
  4888.2 2014.61  4891.0 2014.61  4896.6 2013.91  4910.6 2012.77  4918.9 2011.90
  4924.5 2011.82  4932.9 2010.75  4941.3 2009.30  4946.9 2008.92  4963.7 2005.63
  4969.3 2005.18  4986.0 2003.13  4991.6 2003.43  4997.2 2001.94  5002.5 2001.94
  5008.0 2001.55  5008.3 2001.05  5011.8 2001.05  5012.0 2001.55  5014.8 2002.40
  5020.0 2003.99  5030.0 2005.28  5040.0 2005.68  5060.0 2008.05  5080.0 2009.73
  5116.0 2010.91  5120.0 2011.09  5130.0 2012.20  5140.0 2012.16  5150.0 2012.52
#Mann=5,-1,0
  4888.2     0.1       0  5008.0    0.05       0  5012.0     0.1       0
  5014.8    0.07       0  5116.0     0.1       0
Bank Sta=5008,5012
Exp/Cntr=0.3,0.1

Type RM Length L Ch R = 1,515,276,276,276
BEGIN DESCRIPTION:
Stream0370 1.0
END DESCRIPTION:
XS GIS Cut Line= 3
      1842625.02     13981675.04      1842575.00     13981575.00
      1842475.04     13981525.02
#Sta/Elev= 30
  4887.9 2004.63  4890.7 2004.63  4896.3 2003.99  4901.9 2003.76  4910.3 2003.03
  4924.3 2001.36  4932.7 2000.58  4946.6 1998.06  4955.0 1996.07  4963.4 1995.25
  4969.0 1994.20  4977.4 1993.86  4985.8 1993.71  4991.4 1992.97  4996.9 1992.72
  5002.5 1992.72  5008.1 1992.36  5011.7 1991.92  5012.0 1991.42  5015.5 1991.42
  5015.7 1991.92  5022.1 1994.12  5030.5 1998.24  5036.1 1999.34  5044.5 2000.44
  5066.8 2002.23  5075.2 2002.75  5097.6 2003.69  5103.2 2004.03  5111.5 2004.22
#Mann=3,-1,0
  4887.9     0.1       0  5011.7    0.05       0  5015.7     0.1       0
Bank Sta=5011.7,5015.7
Exp/Cntr=0.3,0.1

Type RM Length L Ch R = 1,239,181,181,181
BEGIN DESCRIPTION:
Stream0370 0.0
END DESCRIPTION:
XS GIS Cut Line= 2
      1842980.60     13981555.81      1842664.61     13981318.97
#Sta/Elev= 30
  4759.8 2010.43  4789.8 2009.20  4821.3 2007.63  4829.3 2006.84  4850.4 2005.67
  4865.0 2005.59  4892.1 2003.47  4900.4 2003.37  4906.7 2002.15  4915.0 2001.79
  4929.3 1999.96  4956.7 1994.44  4971.3 1992.17  4985.9 1990.71  4992.1 1988.05
  5000.5 1985.33  5004.7 1983.15  5005.0 1982.65  5008.5 1982.65  5008.7 1983.15
  5015.0 1985.95  5021.3 1986.62  5029.2 1986.86  5050.5 1988.82  5056.7 1990.52
  5079.2 1993.12  5092.1 1995.59  5106.7 1997.63  5129.2 1999.98  5154.7 2000.94
#Mann=4,-1,0
  4759.8    0.07       0  4789.8     0.1       0  5004.7    0.05       0
  5008.7     0.1       0
Bank Sta=5004.7,5008.7
Exp/Cntr=0.3,0.1

Type RM Length L Ch R = 1,58,0,0,0
BEGIN DESCRIPTION:
Stream0370 0.1
END DESCRIPTION:
XS GIS Cut Line= 4
      1843013.65     13981590.75      1842952.88     13981338.98
      1842887.77     13981258.69      1842629.78     13981230.50
#Sta/Elev= 30
  4710.5 2012.56  4728.9 2011.24  4796.7 2009.72  4839.9 2008.06  4891.3 2004.55
  4896.5 2003.56  4901.6 2003.91  4911.9 2001.72  4932.4 1993.08  4938.4 1989.34
  4943.5 1989.59  4969.0 1982.53  4977.6 1982.82  4985.5 1980.64  4991.9 1981.41
  5004.3 1980.01  5004.6 1979.51  5008.3 1980.01  5013.2 1982.57  5041.5 1984.32
  5085.7 1985.81  5126.0 1988.53  5146.1 1990.95  5196.4 1993.84  5226.6 1996.66
  5243.3 1997.26  5248.3 1996.52  5256.7 1996.70  5286.9 1999.02  5332.4 2000.52
#Mann=4,-1,0
  4710.5    0.07       0  4796.7     0.1       0  5004.3    0.05       0
  5008.3     0.1       0
Bank Sta=5004.3,5008.3
Exp/Cntr=0.3,0.1

Chan Stop Cuts=-1