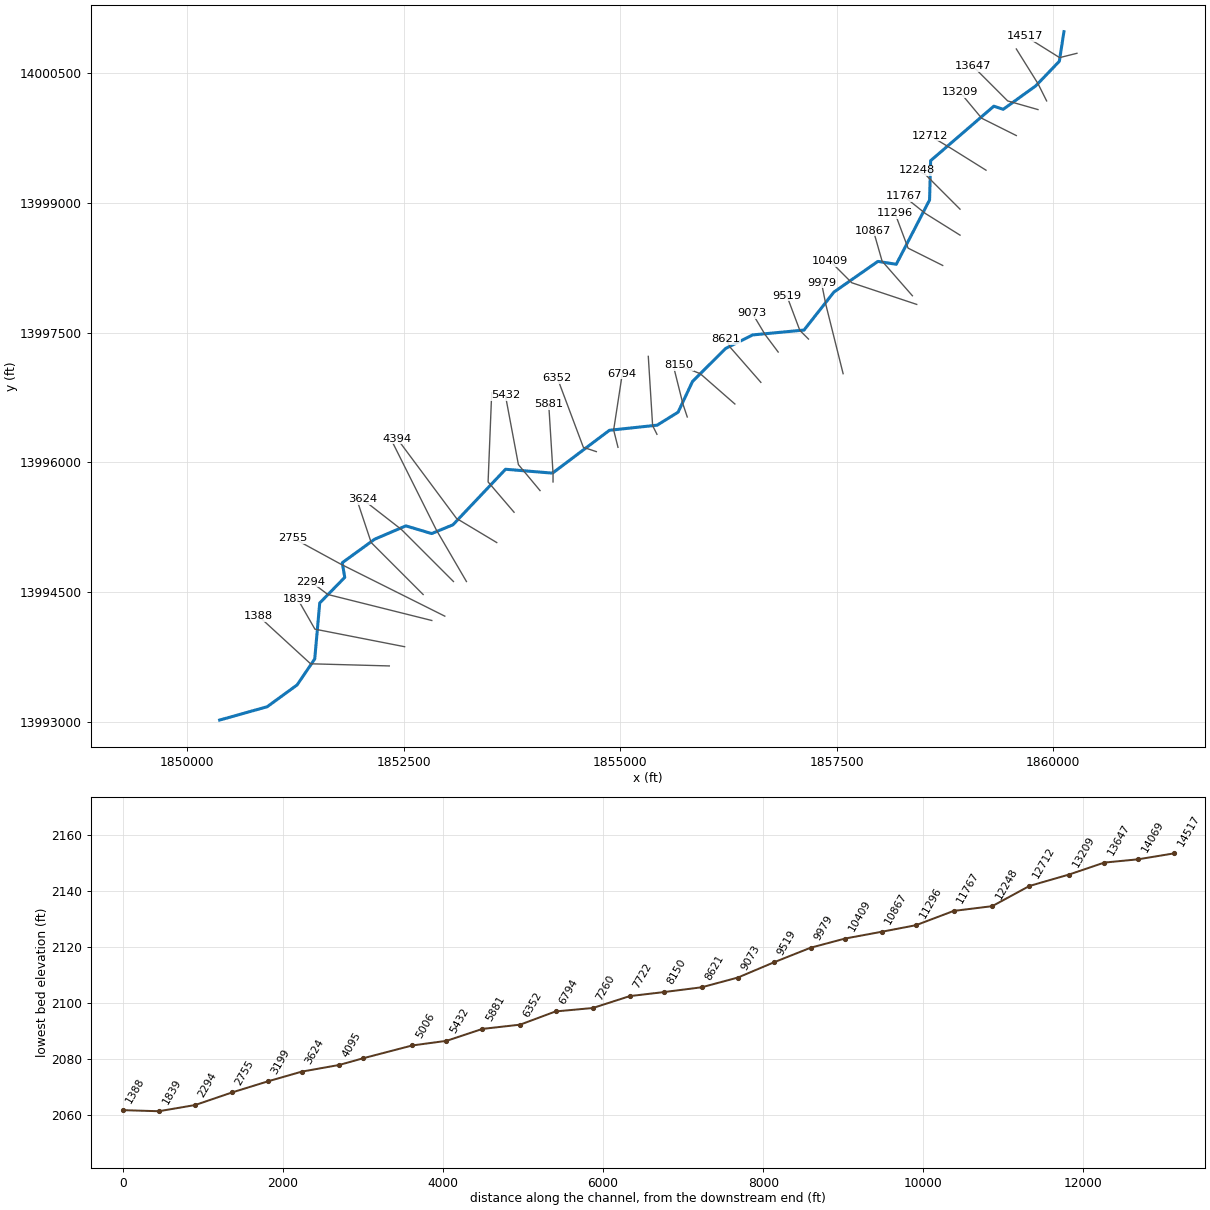
--- Stream0371.prj (project) ---

Proj Title=Stream0371 Base Level Engineering
Current Plan=p01
Default Exp/Contr=0.3,0.1
English Units
Geom File=g01
Flow File=f01
Plan File=p01
BEGIN DESCRIPTION:
Stream0371
END DESCRIPTION:

--- Stream0371.p01 (plan) ---

Plan Title=Multiple Run
Short Identifier=Multiple
Geom File=g01
Flow File=f01
Subcritical Flow
K Sum by GR= 0
Std Step Tol= 0.01
Critical Tol= 0.01
Num of Std Step Trials= 20
Max Error Tol= 0.3
Flow Tol Ratio= 0.001
Split Flow NTrial= 30
Split Flow Tol= 0.02
Split Flow Ratio= 0.02
Log Output Level= 0
Friction Slope Method= 1
Unsteady Friction Slope Method= 2
Unsteady Bridges Friction Slope Method= 1
Parabolic Critical Depth
Global Vel Dist=  1 , 1 , 1
Global Log Level= 0
CheckData=True
Encroach Param= -1, 0, 0, 0
BEGIN DESCRIPTION:
Multiple Run
END DESCRIPTION:

--- Stream0371.f01 (steady flow) ---

Flow Title=Multiple
Number of Profiles=7
Profile Names=10-year,25-year,50-year,1pct_min,100-year,1pct_plu,500-year
River Rch & RM= Stream0371,Reach-1,14517
    1884    3295    4666    3183    6352   12674   11647
River Rch & RM= Stream0371,Reach-1,9979
    2367    4177    5948    4077    8135   16232   15064
River Rch & RM= Stream0371,Reach-1,4394
    3443    6175    8891    6155   12280   24502   23192
Boundary for River Rch & Prof#=Stream0371,Reach-1,1
Up Type=0
Dn Type=3
Dn Slope=0.005
Boundary for River Rch & Prof#=Stream0371,Reach-1,2
Up Type=0
Dn Type=3
Dn Slope=0.005
Boundary for River Rch & Prof#=Stream0371,Reach-1,3
Up Type=0
Dn Type=3
Dn Slope=0.005
Boundary for River Rch & Prof#=Stream0371,Reach-1,4
Up Type=0
Dn Type=3
Dn Slope=0.005
Boundary for River Rch & Prof#=Stream0371,Reach-1,5
Up Type=0
Dn Type=3
Dn Slope=0.005
Boundary for River Rch & Prof#=Stream0371,Reach-1,6
Up Type=0
Dn Type=3
Dn Slope=0.005
Boundary for River Rch & Prof#=Stream0371,Reach-1,7
Up Type=0
Dn Type=3
Dn Slope=0.005

--- Stream0371.g01 (geometry) ---

Geom Title=Existing Conditions

River Reach=Stream0371,Reach-1
Reach XY= 30
      1860125.00     14000975.00      1860071.97     14000633.01
      1859798.47     14000348.01      1859423.57     14000078.07
      1859314.95     14000113.89      1858585.63     13999485.00
      1858573.18     13999031.12      1858188.65     13998288.19
      1857976.64     13998321.86      1857468.54     13997967.25
      1857123.42     13997528.82      1856530.94     13997472.73
      1856218.95     13997316.84      1855835.48     13996934.80
      1855669.39     13996580.59      1855427.42     13996430.54
      1854876.25     13996371.55      1854218.97     13995876.62
      1853676.50     13995921.38      1853069.54     13995280.24
      1852823.45     13995178.75      1852525.08     13995267.70
      1852165.00     13995113.76      1851791.14     13994842.08
      1851819.61     13994672.56      1851530.84     13994377.29
      1851473.04     13993730.89      1851269.38     13993430.62
      1850923.42     13993178.83      1850375.00     13993025.00

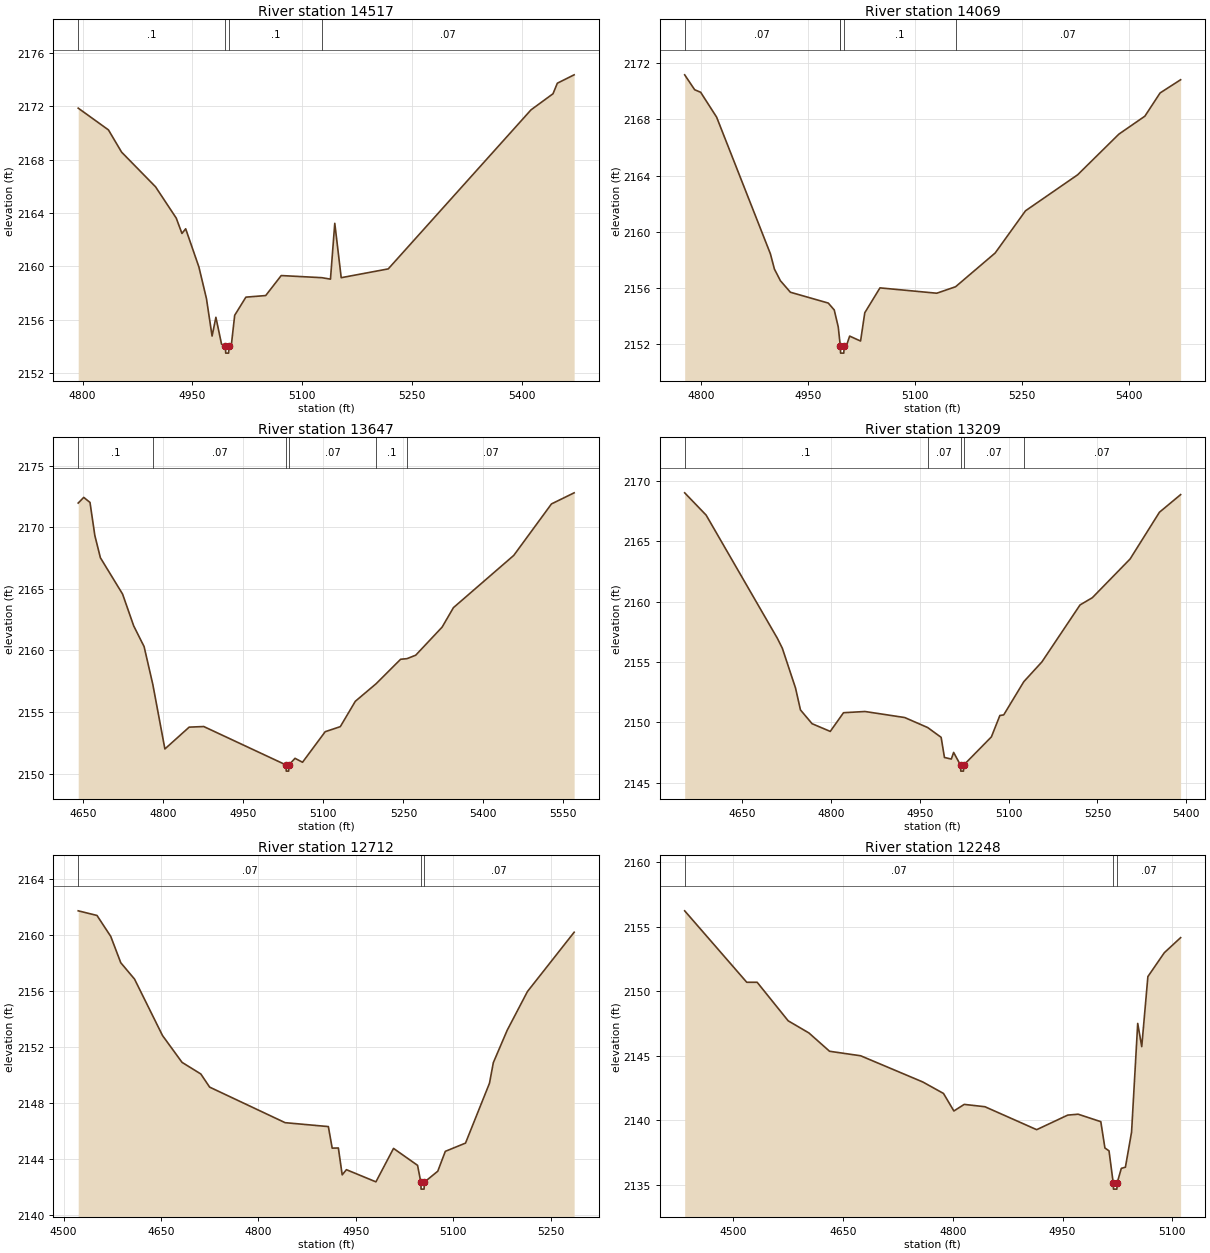
Type RM Length L Ch R = 1,14517,448,448,448
BEGIN DESCRIPTION:
Stream0371 30.0
END DESCRIPTION:
XS GIS Cut Line= 3
      1860275.04     14000725.01      1860075.00     14000675.00
      1859675.00     14000925.00
#Sta/Elev= 30
  4794.0 2171.86  4835.3 2170.23  4853.3 2168.56  4899.7 2165.96  4928.0 2163.61
  4935.8 2162.46  4940.9 2162.81  4959.0 2159.94  4969.3 2157.57  4977.0 2154.76
  4982.2 2156.17  4989.9 2154.16  4995.3 2153.98  4995.6 2153.48  4999.6 2153.48
  5000.0 2153.98  5003.1 2153.98  5007.9 2156.32  5023.2 2157.68  5050.3 2157.80
  5071.5 2159.30  5127.1 2159.14  5138.8 2159.03  5144.7 2163.22  5153.5 2159.14
  5217.8 2159.80  5412.9 2171.73  5443.0 2172.94  5448.9 2173.73  5471.9 2174.36
#Mann=4,-1,0
  4794.0     0.1       0  4995.3    0.05       0  5000.0     0.1       0
  5127.1    0.07       0
Bank Sta=4995.3,5000
Exp/Cntr=0.3,0.1

Type RM Length L Ch R = 1,14069,422,422,422
BEGIN DESCRIPTION:
Stream0371 29.0
END DESCRIPTION:
XS GIS Cut Line= 3
      1859925.02     14000174.97      1859825.00     14000375.00
      1859575.02     14000774.96
#Sta/Elev= 30
  4776.6 2171.16  4790.6 2170.10  4799.0 2169.92  4821.4 2168.15  4896.8 2158.43
  4902.4 2157.35  4910.8 2156.52  4924.8 2155.70  4977.9 2154.93  4986.3 2154.44
  4991.9 2153.23  4994.0 2152.25  4994.8 2151.87  4995.2 2151.37  4999.7 2151.37
  5000.1 2151.87  5003.2 2151.87  5007.9 2152.58  5023.2 2152.23  5029.1 2154.24
  5050.4 2156.01  5130.0 2155.63  5156.4 2156.09  5211.9 2158.49  5254.4 2161.49
  5327.5 2164.05  5385.3 2166.94  5421.8 2168.22  5443.1 2169.87  5471.9 2170.81
#Mann=5,-1,0
  4776.6    0.07       0  4994.0     0.1       0  4994.8    0.05       0
  5000.1     0.1       0  5156.4    0.07       0
Bank Sta=4994.8,5000.1
Exp/Cntr=0.3,0.1

Type RM Length L Ch R = 1,13647,438,438,438
BEGIN DESCRIPTION:
Stream0371 28.0
END DESCRIPTION:
XS GIS Cut Line= 3
      1859824.97     14000075.01      1859475.00     14000175.00
      1859074.97     14000575.03
#Sta/Elev= 30
  4640.4 2171.96  4650.8 2172.42  4662.5 2172.01  4671.6 2169.32  4682.0 2167.52
  4723.6 2164.57  4744.4 2161.99  4763.9 2160.31  4780.3 2157.23  4802.9 2152.00
  4848.4 2153.77  4875.7 2153.82  5030.0 2150.70  5030.4 2150.20  5034.9 2150.20
  5035.3 2150.70  5046.8 2151.24  5060.9 2150.92  5103.4 2153.40  5131.7 2153.81
  5159.9 2155.87  5199.0 2157.30  5244.8 2159.28  5256.8 2159.33  5273.1 2159.61
  5322.6 2161.89  5343.8 2163.47  5456.9 2167.71  5527.6 2171.89  5570.1 2172.79
#Mann=6,-1,0
  4640.4     0.1       0  4780.3    0.07       0  5030.0    0.05       0
  5035.3    0.07       0  5199.0     0.1       0  5256.8    0.07       0
Bank Sta=5030,5035.3
Exp/Cntr=0.3,0.1

Type RM Length L Ch R = 1,13209,497,497,497
BEGIN DESCRIPTION:
Stream0371 27.0
END DESCRIPTION:
XS GIS Cut Line= 3
      1859574.96     13999775.02      1859175.00     13999975.00
      1858924.99     14000275.01
#Sta/Elev= 30
  4552.8 2169.01  4589.1 2167.16  4709.3 2156.96  4717.7 2156.14  4740.0 2152.84
  4748.4 2151.02  4768.0 2149.88  4798.7 2149.24  4821.1 2150.79  4857.4 2150.89
  4924.5 2150.39  4963.3 2149.56  4986.0 2148.75  4991.6 2147.08  5003.2 2146.95
  5007.1 2147.50  5018.7 2146.45  5019.2 2145.95  5023.7 2145.95  5024.1 2146.45
  5070.9 2148.79  5085.2 2150.56  5091.7 2150.61  5125.6 2153.36  5156.2 2155.00
  5220.6 2159.72  5241.4 2160.32  5305.2 2163.53  5354.7 2167.40  5390.5 2168.86
#Mann=5,-1,0
  4552.8     0.1       0  4963.3    0.07       0  5018.7    0.05       0
  5024.1    0.07       0  5125.6    0.07       0
Bank Sta=5018.7,5024.1
Exp/Cntr=0.3,0.1

Type RM Length L Ch R = 1,12712,464,464,464
BEGIN DESCRIPTION:
Stream0371 26.0
END DESCRIPTION:
XS GIS Cut Line= 3
      1859225.02     13999374.99      1858825.00     13999625.00
      1858574.98     13999775.01
#Sta/Elev= 30
  4522.6 2161.74  4551.5 2161.41  4572.7 2159.91  4588.1 2158.03  4609.3 2156.86
  4652.3 2152.83  4682.4 2150.91  4711.3 2150.08  4724.9 2149.14  4841.0 2146.60
  4907.6 2146.32  4913.5 2144.78  4923.0 2144.79  4928.9 2142.87  4935.4 2143.24
  4980.8 2142.37  5007.9 2144.76  5044.9 2143.55  5049.9 2142.35  5050.3 2141.85
  5054.9 2141.85  5055.4 2142.35  5076.0 2143.13  5087.6 2144.55  5118.7 2145.14
  5155.6 2149.42  5161.5 2150.89  5182.9 2153.21  5214.0 2155.97  5285.9 2160.21
#Mann=3,-1,0
  4522.6    0.07       0  5049.9    0.05       0  5055.4    0.07       0
Bank Sta=5049.9,5055.4
Exp/Cntr=0.3,0.1

Type RM Length L Ch R = 1,12248,481,481,481
BEGIN DESCRIPTION:
Stream0371 25.0
END DESCRIPTION:
XS GIS Cut Line= 3
      1858924.97     13998925.03      1858525.00     13999325.00
      1858425.04     13999374.98
#Sta/Elev= 30
  4433.9 2156.23  4518.7 2150.69  4532.9 2150.69  4575.3 2147.70  4603.6 2146.76
  4631.8 2145.34  4674.3 2144.99  4759.1 2142.96  4787.4 2142.07  4801.6 2140.71
  4815.7 2141.22  4844.0 2141.04  4914.7 2139.26  4957.1 2140.39  4971.3 2140.46
  5002.3 2139.88  5007.9 2137.84  5013.5 2137.62  5019.2 2135.15  5019.6 2134.65
  5024.2 2134.65  5024.7 2135.15  5030.3 2136.26  5035.9 2136.35  5044.3 2139.07
  5052.7 2147.50  5058.2 2145.70  5066.6 2151.13  5089.0 2152.98  5111.3 2154.15
#Mann=3,-1,0
  4433.9    0.07       0  5019.2    0.05       0  5024.7    0.07       0
Bank Sta=5019.2,5024.7
Exp/Cntr=0.3,0.1

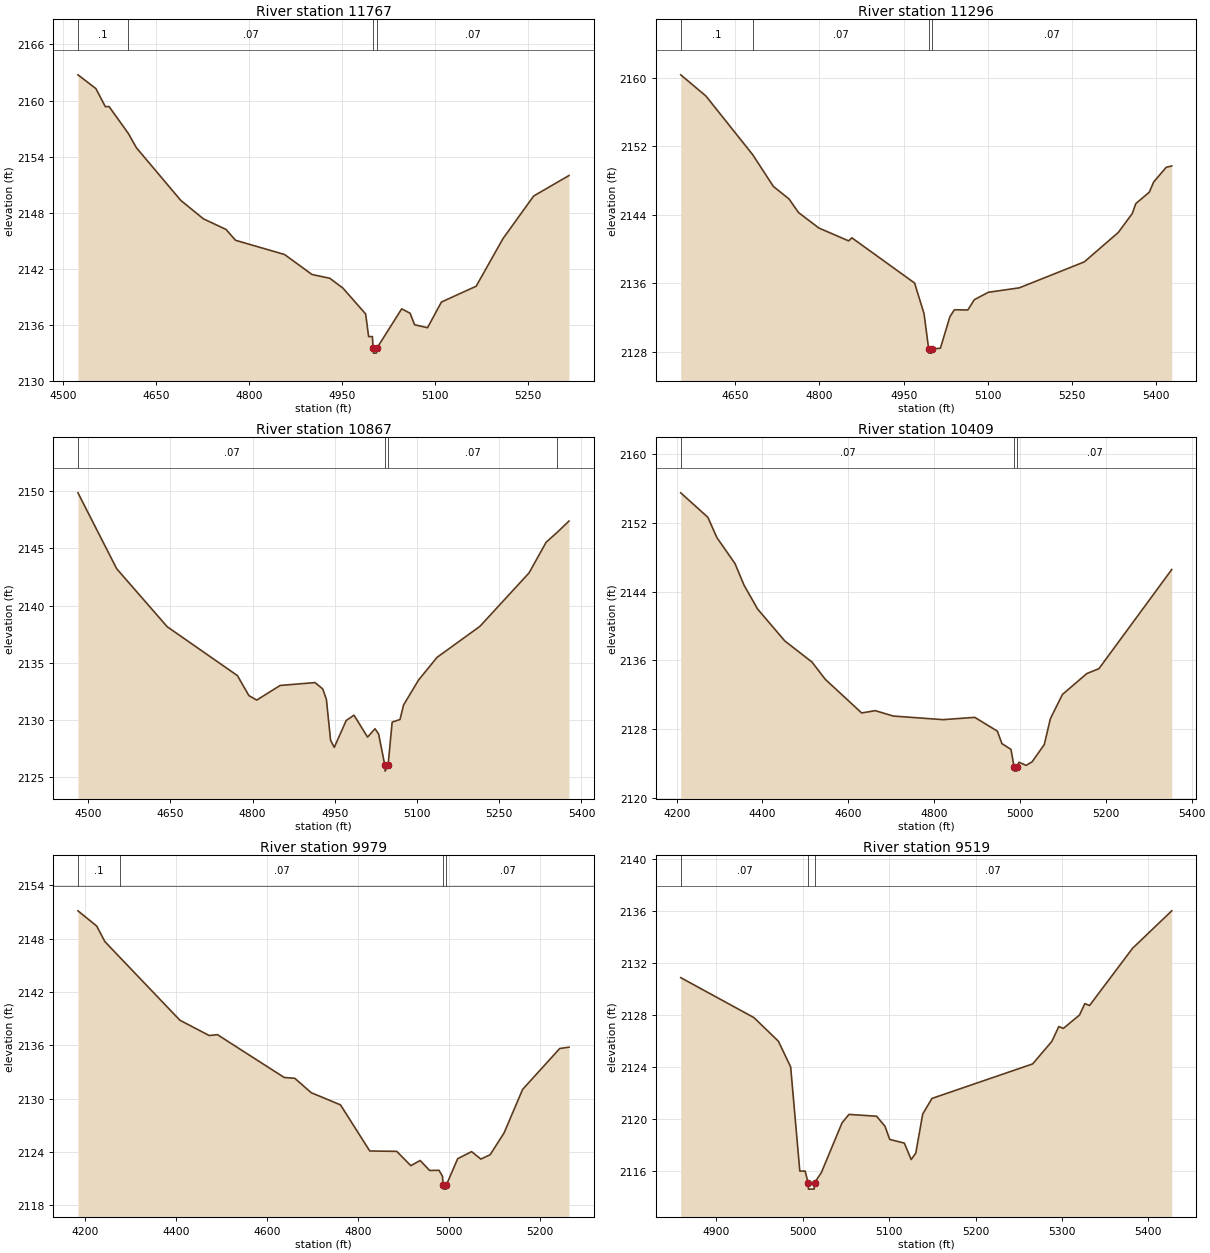
Type RM Length L Ch R = 1,11767,471,471,471
BEGIN DESCRIPTION:
Stream0371 24.0
END DESCRIPTION:
XS GIS Cut Line= 3
      1858925.01     13998625.00      1858525.00     13998875.00
      1858274.97     13999075.02
#Sta/Elev= 30
  4523.9 2162.75  4552.8 2161.28  4568.1 2159.34  4574.0 2159.36  4605.1 2156.48
  4618.2 2154.94  4689.6 2149.32  4726.1 2147.34  4762.7 2146.20  4778.0 2145.04
  4857.0 2143.52  4901.3 2141.38  4930.2 2140.97  4951.4 2139.91  4987.9 2137.15
  4992.7 2134.73  4998.8 2134.73  5000.0 2133.46  5000.4 2132.96  5005.2 2132.96
  5005.7 2133.46  5046.0 2137.70  5059.6 2137.23  5066.8 2136.00  5087.7 2135.68
  5110.1 2138.43  5166.1 2140.12  5209.3 2145.21  5258.9 2149.78  5315.8 2151.97
#Mann=4,-1,0
  4523.9     0.1       0  4605.1    0.07       0  5000.0    0.05       0
  5005.7    0.07       0
Bank Sta=5000,5005.7
Exp/Cntr=0.3,0.1

Type RM Length L Ch R = 1,11296,429,429,429
BEGIN DESCRIPTION:
Stream0371 23.0
END DESCRIPTION:
XS GIS Cut Line= 3
      1858725.02     13998274.99      1858325.00     13998475.00
      1858175.01     13998874.97
#Sta/Elev= 30
  4552.9 2160.34  4597.6 2157.88  4681.3 2151.00  4717.8 2147.32  4745.8 2145.85
  4762.6 2144.27  4798.9 2142.46  4852.0 2140.96  4857.6 2141.32  4969.4 2136.04
  4986.2 2132.47  4994.4 2128.36  4994.9 2127.86  4999.7 2127.86  5000.2 2128.36
  5015.3 2128.43  5032.2 2132.10  5040.2 2132.92  5064.2 2132.90  5075.8 2134.10
  5100.7 2134.96  5155.9 2135.48  5271.6 2138.51  5332.1 2141.94  5357.0 2144.15
  5363.3 2145.31  5387.3 2146.64  5395.3 2147.85  5417.5 2149.55  5427.3 2149.70
#Mann=4,-1,0
  4552.9     0.1       0  4681.3    0.07       0  4994.4    0.05       0
  5000.2    0.07       0
Bank Sta=4994.4,5000.2
Exp/Cntr=0.3,0.1

Type RM Length L Ch R = 1,10867,458,458,458
BEGIN DESCRIPTION:
Stream0371 22.0
END DESCRIPTION:
XS GIS Cut Line= 3
      1858375.03     13997924.97      1858025.00     13998325.00
      1857924.99     13998675.05
#Sta/Elev= 30
  4481.6 2149.87  4552.3 2143.22  4644.4 2138.15  4772.5 2133.87  4793.4 2132.12
  4807.7 2131.73  4850.4 2133.01  4914.0 2133.26  4928.2 2132.70  4934.8 2131.77
  4942.4 2128.21  4949.1 2127.59  4970.9 2129.94  4985.1 2130.41  5009.8 2128.49
  5023.5 2129.22  5030.0 2128.76  5041.4 2126.01  5041.9 2125.51  5047.2 2126.01
  5054.7 2129.80  5069.0 2130.03  5075.5 2131.30  5102.8 2133.48  5136.6 2135.47
  5214.7 2138.18  5304.4 2142.86  5335.6 2145.55  5356.2 2146.43  5377.2 2147.40
#Mann=4,-1,0
  4481.6    0.07       0  5041.4    0.05       0  5047.2    0.07       0
  5356.2     0.1       0
Bank Sta=5041.4,5047.2
Exp/Cntr=0.3,0.1

Type RM Length L Ch R = 1,10409,430,430,430
BEGIN DESCRIPTION:
Stream0371 21.0
END DESCRIPTION:
XS GIS Cut Line= 3
      1858424.98     13997825.01      1857675.00     13998075.00
      1857425.00     13998325.00
#Sta/Elev= 30
  4209.5 2155.53  4272.7 2152.68  4293.8 2150.31  4336.0 2147.28  4357.1 2144.76
  4388.7 2141.98  4451.9 2138.27  4515.2 2135.81  4546.8 2133.77  4631.1 2129.87
  4662.7 2130.14  4704.9 2129.51  4820.9 2129.09  4894.6 2129.36  4947.3 2127.75
  4957.9 2126.30  4979.0 2125.62  4986.3 2123.59  4986.8 2123.09  4992.3 2123.09
  4992.8 2123.59  4997.4 2124.13  5014.2 2123.76  5028.3 2124.18  5056.6 2126.19
  5070.8 2129.20  5099.0 2132.03  5155.6 2134.46  5183.9 2135.03  5353.6 2146.59
#Mann=3,-1,0
  4209.5    0.07       0  4986.3    0.05       0  4992.8    0.07       0
Bank Sta=4986.3,4992.8
Exp/Cntr=0.3,0.1

Type RM Length L Ch R = 1,9979,460,460,460
BEGIN DESCRIPTION:
Stream0371 20.0
END DESCRIPTION:
XS GIS Cut Line= 3
      1857574.99     13997025.03      1857375.00     13997825.00
      1857325.01     13998074.95
#Sta/Elev= 30
  4184.3 2151.12  4225.5 2149.41  4243.5 2147.66  4277.3 2145.84  4408.5 2138.81
  4472.9 2137.09  4490.9 2137.19  4637.8 2132.37  4661.0 2132.28  4697.1 2130.66
  4761.5 2129.29  4825.9 2124.10  4885.2 2124.06  4916.1 2122.45  4936.7 2123.03
  4957.4 2121.91  4978.0 2121.93  4985.7 2121.26  4987.2 2120.31  4987.7 2119.81
  4994.0 2119.81  4994.5 2120.31  5019.1 2123.23  5049.7 2124.03  5070.1 2123.19
  5090.5 2123.68  5121.1 2126.13  5161.9 2131.03  5243.5 2135.63  5263.8 2135.78
#Mann=4,-1,0
  4184.3     0.1       0  4277.3    0.07       0  4987.2    0.05       0
  4994.5    0.07       0
Bank Sta=4987.2,4994.5
Exp/Cntr=0.3,0.1

Type RM Length L Ch R = 1,9519,446,446,446
BEGIN DESCRIPTION:
Stream0371 19.0
END DESCRIPTION:
XS GIS Cut Line= 3
      1857174.99     13997425.01      1857075.00     13997525.00
      1856925.00     13997924.99
#Sta/Elev= 30
  4858.6 2130.88  4943.4 2127.80  4971.7 2125.98  4985.9 2124.00  4996.5 2115.97
  5002.7 2115.97  5006.0 2115.08  5006.5 2114.58  5013.1 2114.58  5013.6 2115.08
  5021.4 2115.85  5045.4 2119.69  5053.4 2120.34  5085.4 2120.20  5095.2 2119.42
  5100.6 2118.41  5117.5 2118.13  5125.5 2116.86  5130.8 2117.36  5138.8 2120.36
  5149.5 2121.57  5266.1 2124.23  5288.4 2125.97  5296.4 2127.11  5301.7 2126.97
  5320.4 2128.00  5326.6 2128.88  5332.0 2128.73  5381.8 2133.14  5427.2 2136.03
#Mann=3,-1,0
  4858.6    0.07       0  5006.0    0.05       0  5013.6    0.07       0
Bank Sta=5006,5013.6
Exp/Cntr=0.3,0.1

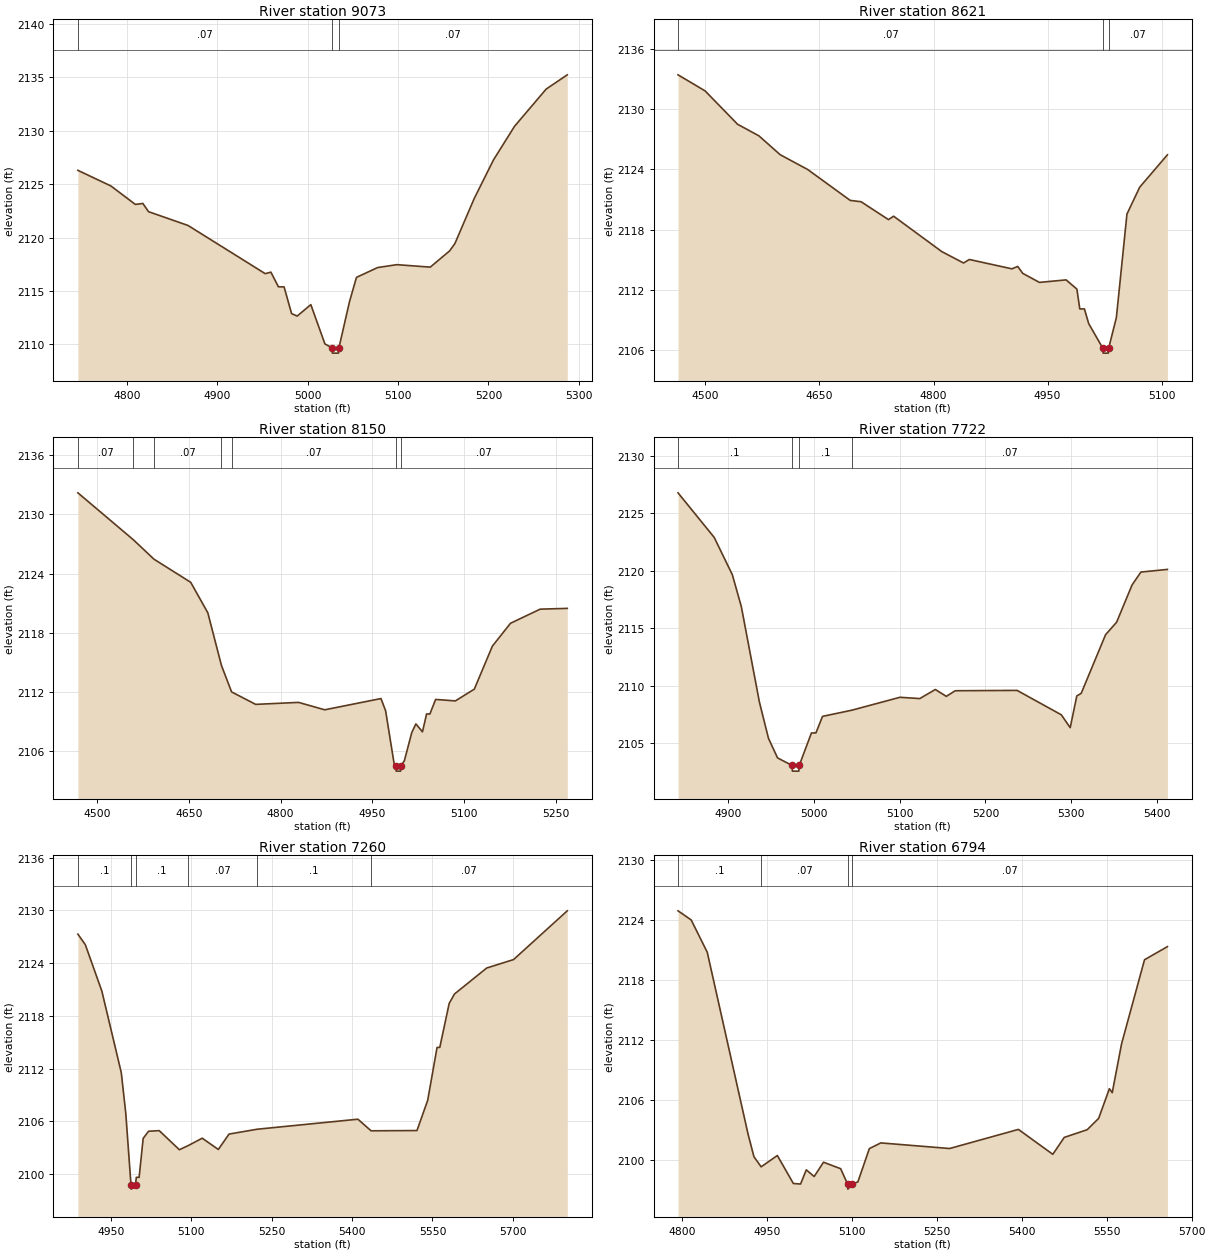
Type RM Length L Ch R = 1,9073,452,452,452
BEGIN DESCRIPTION:
Stream0371 18.0
END DESCRIPTION:
XS GIS Cut Line= 3
      1856825.02     13997274.98      1856675.00     13997475.00
      1856524.99     13997725.02
#Sta/Elev= 30
  4745.6 2126.30  4782.1 2124.84  4809.2 2123.11  4817.5 2123.20  4823.8 2122.43
  4867.5 2121.14  4952.9 2116.63  4959.2 2116.77  4967.5 2115.40  4973.8 2115.39
  4982.1 2112.89  4988.3 2112.66  5003.4 2113.73  5019.0 2110.05  5026.8 2109.69
  5027.3 2109.19  5034.0 2109.19  5034.5 2109.69  5046.2 2114.01  5053.9 2116.28
  5077.3 2117.20  5098.6 2117.47  5135.6 2117.24  5157.0 2118.76  5162.8 2119.44
  5184.2 2123.66  5205.5 2127.27  5228.9 2130.43  5263.9 2133.91  5287.2 2135.24
#Mann=3,-1,0
  4745.6    0.07       0  5026.8    0.05       0  5034.5    0.07       0
Bank Sta=5026.8,5034.5
Exp/Cntr=0.3,0.1

Type RM Length L Ch R = 1,8621,471,471,471
BEGIN DESCRIPTION:
Stream0371 17.0
END DESCRIPTION:
XS GIS Cut Line= 3
      1856625.03     13996924.97      1856275.00     13997325.00
      1856224.98     13997425.04
#Sta/Elev= 30
  4464.1 2133.41  4499.7 2131.81  4542.4 2128.49  4570.4 2127.34  4598.4 2125.46
  4634.5 2123.99  4690.5 2120.91  4704.7 2120.78  4740.8 2119.00  4747.5 2119.34
  4811.0 2115.81  4839.5 2114.68  4847.1 2115.03  4903.1 2114.10  4910.7 2114.34
  4917.3 2113.65  4939.2 2112.75  4974.3 2113.00  4988.5 2112.08  4992.3 2110.11
  4998.4 2110.11  5004.0 2108.65  5022.5 2106.21  5023.0 2105.71  5029.8 2105.71
  5030.3 2106.21  5040.4 2109.25  5054.3 2119.55  5071.1 2122.23  5107.5 2125.45
#Mann=3,-1,0
  4464.1    0.07       0  5022.5    0.05       0  5030.3    0.07       0
Bank Sta=5022.5,5030.3
Exp/Cntr=0.3,0.1

Type RM Length L Ch R = 1,8150,428,428,428
BEGIN DESCRIPTION:
Stream0371 16.0
END DESCRIPTION:
XS GIS Cut Line= 3
      1856324.97     13996675.03      1855925.00     13997025.00
      1855675.02     13997124.99
#Sta/Elev= 30
  4468.5 2132.18  4559.4 2127.42  4593.0 2125.46  4653.1 2123.12  4681.1 2120.03
  4703.4 2114.70  4720.0 2112.02  4759.4 2110.76  4829.6 2110.96  4872.3 2110.21
  4964.4 2111.35  4972.0 2110.11  4986.2 2104.64  4988.8 2104.50  4989.3 2104.00
  4996.4 2104.00  4996.9 2104.50  5002.7 2105.06  5014.8 2107.91  5021.5 2108.78
  5032.3 2107.98  5039.0 2109.79  5044.4 2109.78  5053.8 2111.26  5086.1 2111.11
  5117.1 2112.30  5146.7 2116.66  5176.3 2118.97  5224.8 2120.40  5269.2 2120.48
#Mann=7,-1,0
  4468.5    0.07       0  4559.4     0.1       0  4593.0    0.07       0
  4703.4     0.1       0  4720.0    0.07       0  4988.8    0.05       0
  4996.9    0.07       0
Bank Sta=4988.8,4996.9
Exp/Cntr=0.3,0.1

Type RM Length L Ch R = 1,7722,462,462,462
BEGIN DESCRIPTION:
Stream0371 15.0
END DESCRIPTION:
XS GIS Cut Line= 3
      1855775.00     13996524.99      1855725.00     13996675.00
      1855625.01     13997074.96
#Sta/Elev= 30
  4841.7 2126.76  4883.9 2122.88  4905.0 2119.64  4915.5 2116.86  4936.6 2108.55
  4947.1 2105.42  4957.7 2103.71  4974.5 2103.06  4975.0 2102.56  4982.5 2102.56
  4983.0 2103.06  4997.2 2105.88  5002.4 2105.88  5010.1 2107.32  5044.4 2107.86
  5100.3 2108.98  5123.5 2108.87  5141.6 2109.66  5154.4 2109.06  5164.8 2109.55
  5236.9 2109.58  5288.4 2107.46  5298.8 2106.34  5306.5 2109.10  5311.6 2109.32
  5340.0 2114.42  5352.9 2115.51  5370.9 2118.75  5381.2 2119.87  5412.1 2120.10
#Mann=4,-1,0
  4841.7     0.1       0  4974.5    0.05       0  4983.0     0.1       0
  5044.4    0.07       0
Bank Sta=4974.5,4983
Exp/Cntr=0.3,0.1

Type RM Length L Ch R = 1,7260,466,466,466
BEGIN DESCRIPTION:
Stream0371 14.0
END DESCRIPTION:
XS GIS Cut Line= 3
      1855424.98     13996325.04      1855375.00     13996425.00
      1855325.00     13997224.98
#Sta/Elev= 30
  4888.3 2127.30  4902.2 2126.10  4933.0 2120.83  4969.3 2111.55  4977.7 2106.92
  4987.4 2098.81  4987.9 2098.31  4995.9 2098.81  4997.3 2099.65  5002.6 2099.65
  5010.1 2104.07  5020.1 2104.89  5040.1 2104.96  5077.7 2102.79  5094.5 2103.27
  5120.3 2104.10  5150.4 2102.82  5170.4 2104.57  5223.0 2105.12  5410.9 2106.26
  5435.5 2104.94  5521.1 2104.97  5541.1 2108.40  5558.6 2114.42  5563.7 2114.42
  5581.2 2119.42  5591.2 2120.50  5651.3 2123.45  5701.4 2124.41  5801.6 2129.95
#Mann=6,-1,0
  4888.3     0.1       0  4987.4    0.05       0  4995.9     0.1       0
  5094.5    0.07       0  5223.0     0.1       0  5435.5    0.07       0
Bank Sta=4987.4,4995.9
Exp/Cntr=0.3,0.1

Type RM Length L Ch R = 1,6794,442,442,442
BEGIN DESCRIPTION:
Stream0371 13.0
END DESCRIPTION:
XS GIS Cut Line= 3
      1854975.01     13996174.98      1854925.00     13996375.00
      1855025.00     13997024.97
#Sta/Elev= 30
  4793.4 2124.90  4816.6 2123.99  4845.0 2120.76  4917.1 2102.56  4927.4 2100.32
  4940.1 2099.31  4968.7 2100.44  4997.0 2097.64  5009.7 2097.59  5019.8 2099.01
  5033.7 2098.34  5050.2 2099.77  5080.5 2099.12  5092.7 2097.58  5093.2 2097.08
  5101.2 2097.58  5110.9 2097.81  5131.1 2101.13  5151.3 2101.70  5272.8 2101.14
  5394.2 2103.05  5454.9 2100.56  5475.1 2102.25  5515.6 2103.02  5535.8 2104.15
  5554.8 2107.12  5559.8 2106.72  5576.3 2111.61  5616.8 2120.01  5657.2 2121.32
#Mann=4,-1,0
  4793.4     0.1       0  4940.1    0.07       0  5092.7    0.05       0
  5101.2    0.07       0
Bank Sta=5092.7,5101.2
Exp/Cntr=0.3,0.1

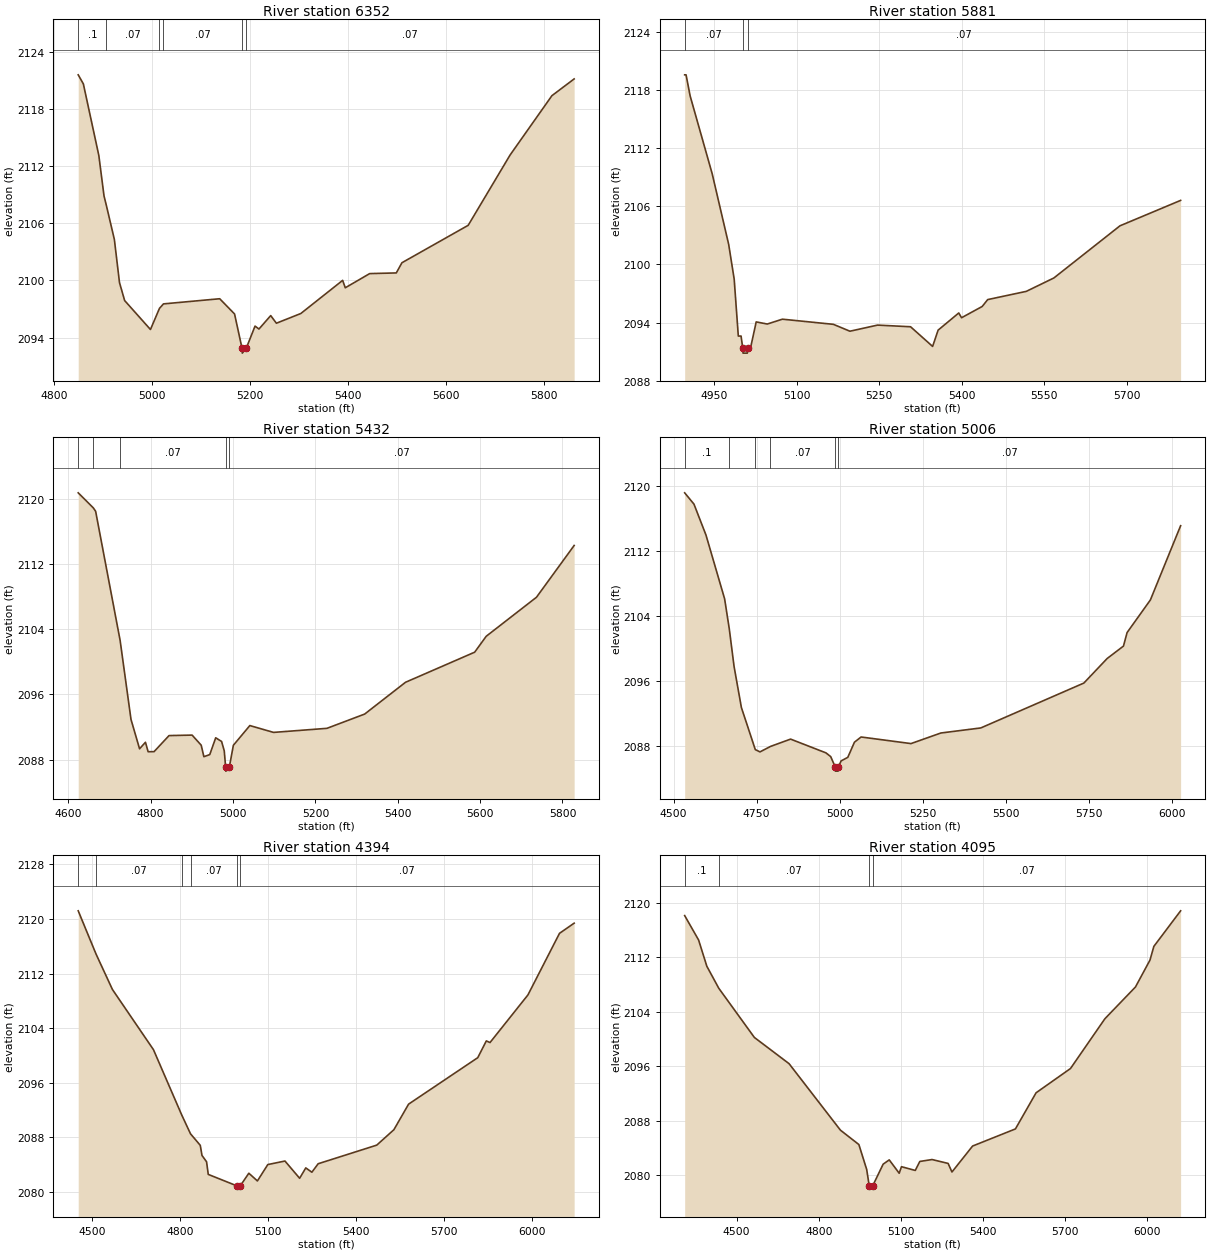
Type RM Length L Ch R = 1,6352,471,471,471
BEGIN DESCRIPTION:
Stream0371 12.0
END DESCRIPTION:
XS GIS Cut Line= 3
      1854724.97     13996125.01      1854575.00     13996175.00
      1854275.00     13996975.01
#Sta/Elev= 30
  4849.2 2121.59  4859.7 2120.64  4891.3 2113.12  4901.9 2108.87  4906.8 2107.85
  4923.0 2104.31  4933.5 2099.77  4944.0 2097.89  4996.7 2094.85  5015.1 2097.07
  5023.3 2097.54  5138.1 2098.08  5168.4 2096.48  5183.7 2092.87  5184.2 2092.37
  5192.2 2092.87  5210.2 2095.21  5218.2 2094.90  5242.2 2096.31  5253.8 2095.51
  5303.7 2096.53  5389.1 2100.01  5394.4 2099.23  5444.3 2100.72  5498.6 2100.79
  5510.1 2101.86  5645.4 2105.79  5730.9 2113.17  5816.3 2119.40  5861.7 2121.16
#Mann=6,-1,0
  4849.2     0.1       0  4906.8    0.07       0  5015.1     0.1       0
  5023.3    0.07       0  5183.7    0.05       0  5192.2    0.07       0
Bank Sta=5183.7,5192.2
Exp/Cntr=0.3,0.1

Type RM Length L Ch R = 1,5881,449,449,449
BEGIN DESCRIPTION:
Stream0371 11.0
END DESCRIPTION:
XS GIS Cut Line= 3
      1854225.00     13995775.03      1854225.00     13995875.00
      1854175.00     13996674.97
#Sta/Elev= 30
  4896.2 2119.55  4898.7 2119.55  4906.2 2117.36  4946.2 2109.35  4976.2 2102.06
  4986.2 2098.48  4993.7 2092.61  4998.7 2092.61  5001.8 2091.35  5002.3 2090.85
  5010.1 2090.85  5010.6 2091.35  5016.2 2091.46  5026.2 2094.07  5046.3 2093.85
  5073.8 2094.35  5166.5 2093.82  5196.6 2093.11  5246.7 2093.74  5306.8 2093.57
  5346.9 2091.54  5356.9 2093.22  5394.4 2094.99  5399.5 2094.50  5437.0 2095.66
  5447.0 2096.37  5517.2 2097.22  5567.3 2098.60  5687.5 2103.98  5797.7 2106.60
#Mann=3,-1,0
  4896.2    0.07       0  5001.8    0.05       0  5010.6    0.07       0
Bank Sta=5001.8,5010.6
Exp/Cntr=0.3,0.1

Type RM Length L Ch R = 1,5432,426,426,426
BEGIN DESCRIPTION:
Stream0371 10.0
END DESCRIPTION:
XS GIS Cut Line= 3
      1854074.98     13995675.02      1853825.00     13995975.00
      1853675.00     13996774.97
#Sta/Elev= 30
  4624.0 2120.73  4660.7 2118.88  4666.3 2118.47  4725.8 2102.62  4752.2 2092.93
  4773.0 2089.33  4787.3 2090.13  4793.8 2088.97  4808.2 2088.98  4844.6 2090.95
  4900.6 2091.01  4922.7 2089.77  4929.2 2088.36  4943.5 2088.62  4957.9 2090.68
  4972.2 2090.23  4978.7 2089.07  4982.0 2087.09  4982.5 2086.59  4991.0 2087.09
  5000.8 2089.76  5040.8 2092.18  5098.4 2091.34  5228.1 2091.84  5319.7 2093.59
  5418.9 2097.49  5586.8 2101.18  5614.8 2103.13  5736.9 2107.92  5828.4 2114.27
#Mann=5,-1,0
  4624.0    0.07       0  4660.7     0.1       0  4725.8    0.07       0
  4982.0    0.05       0  4991.0    0.07       0
Bank Sta=4982,4991
Exp/Cntr=0.3,0.1

Type RM Length L Ch R = 1,5006,612,612,612
BEGIN DESCRIPTION:
Stream0371 9.0
END DESCRIPTION:
XS GIS Cut Line= 3
      1853775.00     13995425.00      1853475.00     13995775.00
      1853516.80     13996805.97
#Sta/Elev= 30
  4533.5 2119.11  4561.5 2117.72  4597.7 2113.92  4653.7 2106.10  4667.6 2102.46
  4682.2 2097.79  4704.2 2092.76  4746.1 2087.59  4760.2 2087.31  4791.8 2087.98
  4852.3 2088.88  4958.8 2087.19  4973.1 2086.73  4986.7 2085.45  4987.2 2084.95
  4995.2 2084.95  4995.7 2085.45  5004.5 2086.21  5024.5 2086.64  5044.5 2088.50
  5064.5 2089.14  5214.7 2088.33  5304.7 2089.63  5424.8 2090.25  5735.1 2095.76
  5805.1 2098.77  5854.3 2100.30  5865.2 2101.96  5935.3 2105.96  6026.3 2115.07
#Mann=6,-1,0
  4533.5     0.1       0  4667.6    0.07       0  4746.1     0.1       0
  4791.8    0.07       0  4986.7    0.05       0  4995.7    0.07       0
Bank Sta=4986.7,4995.7
Exp/Cntr=0.3,0.1

Type RM Length L Ch R = 1,4394,299,299,299
BEGIN DESCRIPTION:
Stream0371 8.0
END DESCRIPTION:
XS GIS Cut Line= 3
      1853574.97     13995075.02      1853110.33     13995353.62
      1852424.98     13996275.02
#Sta/Elev= 30
  4453.1 2121.20  4513.8 2114.87  4569.7 2109.67  4709.6 2100.84  4806.2 2091.24
  4835.8 2088.51  4869.1 2086.82  4874.9 2085.34  4890.5 2084.41  4896.3 2082.56
  4992.7 2080.90  4993.2 2080.40  5005.6 2080.90  5034.6 2082.73  5063.8 2081.60
  5099.2 2084.00  5157.7 2084.52  5207.7 2081.99  5228.6 2083.51  5249.4 2082.88
  5270.8 2084.12  5470.5 2086.85  5528.9 2089.11  5579.0 2092.86  5814.7 2099.67
  5843.9 2102.13  5856.5 2101.89  5985.7 2108.87  6093.3 2117.90  6143.2 2119.39
#Mann=6,-1,0
  4453.1     0.1       0  4513.8    0.07       0  4806.2   0.035       0
  4835.8    0.07       0  4992.7    0.05       0  5005.6    0.07       0
Bank Sta=4992.7,5005.6
Exp/Cntr=0.3,0.1

Type RM Length L Ch R = 1,4095,471,471,471
BEGIN DESCRIPTION:
Stream0371 7.0
END DESCRIPTION:
XS GIS Cut Line= 3
      1853225.00     13994625.00      1852875.00     13995225.00
      1852374.98     13996225.04
#Sta/Elev= 30
  4310.0 2118.12  4360.9 2114.54  4391.0 2110.69  4434.7 2107.46  4564.7 2100.25
  4691.6 2096.40  4879.3 2086.65  4946.7 2084.54  4975.3 2080.88  4984.5 2078.50
  4985.0 2078.00  4997.5 2078.50  5035.4 2081.66  5057.7 2082.29  5094.1 2080.33
  5102.4 2081.29  5152.8 2080.74  5169.5 2082.06  5214.2 2082.34  5272.9 2081.77
  5286.9 2080.51  5362.4 2084.32  5518.9 2086.83  5594.4 2092.13  5720.2 2095.69
  5845.9 2102.99  5957.7 2107.65  6010.8 2111.60  6024.8 2113.60  6122.7 2118.82
#Mann=4,-1,0
  4310.0     0.1       0  4434.7    0.07       0  4984.5    0.05       0
  4997.5    0.07       0
Bank Sta=4984.5,4997.5
Exp/Cntr=0.3,0.1

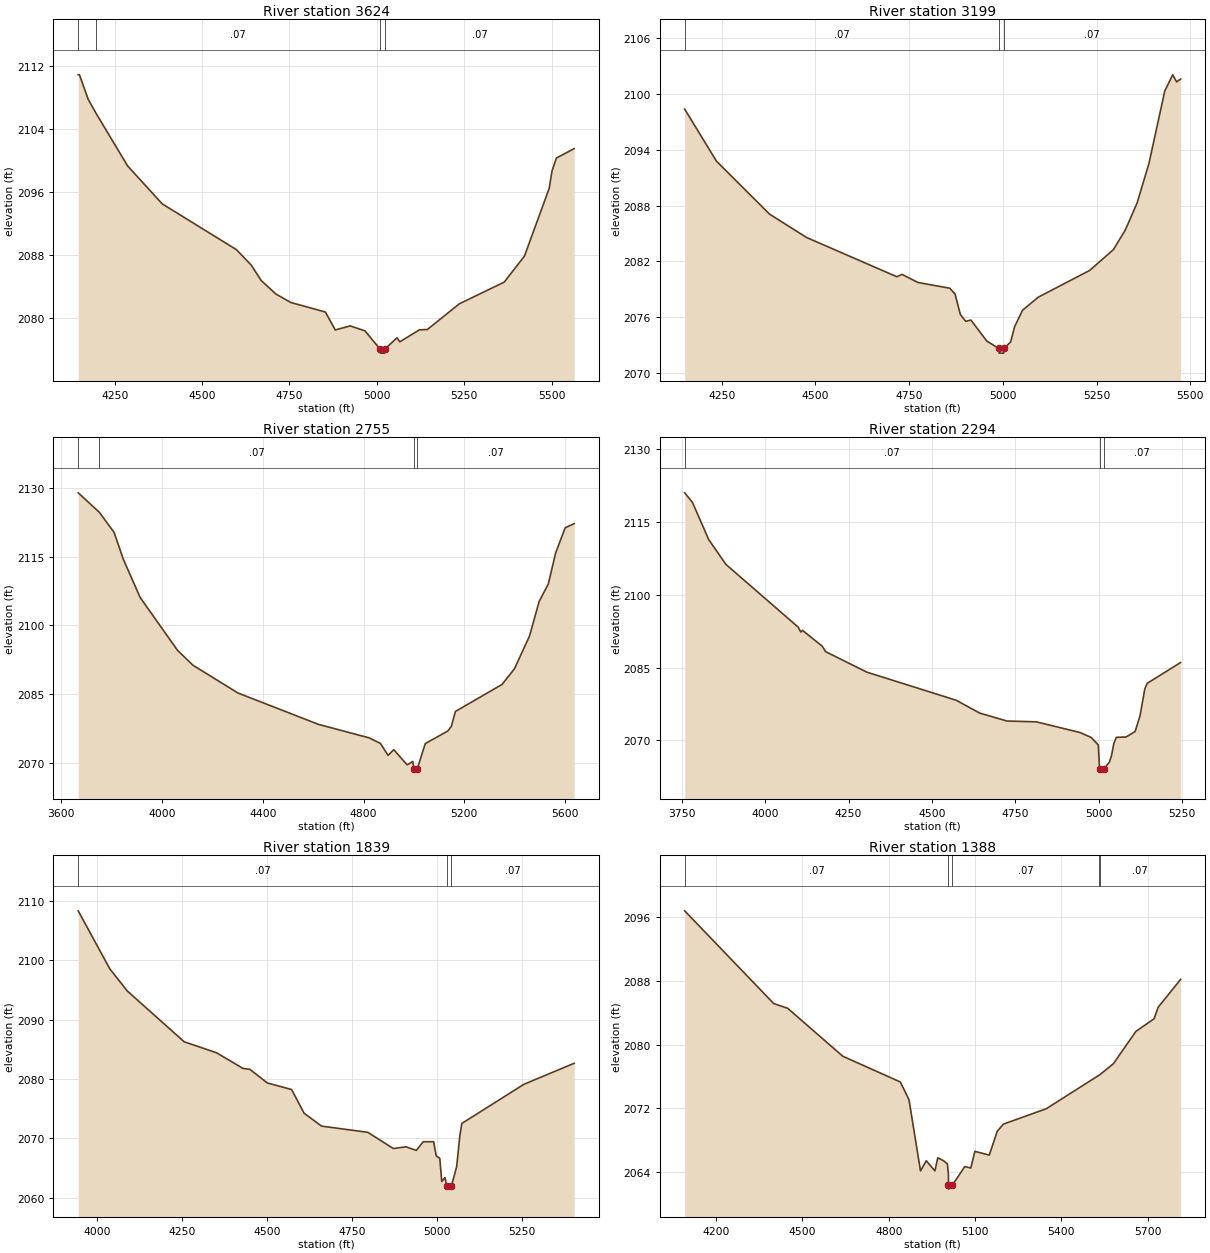
Type RM Length L Ch R = 1,3624,425,425,425
BEGIN DESCRIPTION:
Stream0371 6.0
END DESCRIPTION:
XS GIS Cut Line= 3
      1853075.03     13994624.97      1852475.00     13995225.00
      1852024.96     13995575.03
#Sta/Elev= 30
  4145.8 2110.94  4149.4 2110.94  4174.1 2107.86  4196.7 2106.06  4287.3 2099.36
  4386.3 2094.55  4598.4 2088.74  4640.8 2086.78  4669.1 2084.83  4711.5 2083.10
  4753.9 2082.03  4852.9 2080.82  4881.2 2078.54  4923.7 2079.06  4966.1 2078.43
  5009.5 2076.10  5010.0 2075.60  5022.1 2075.60  5022.6 2076.10  5057.7 2077.55
  5065.9 2077.04  5122.0 2078.56  5144.6 2078.60  5236.0 2081.86  5364.5 2084.62
  5422.4 2087.93  5493.0 2096.51  5501.1 2098.72  5513.8 2100.37  5564.5 2101.57
#Mann=4,-1,0
  4145.8     0.1       0  4196.7    0.07       0  5009.5    0.05       0
  5022.6    0.07       0
Bank Sta=5009.5,5022.6
Exp/Cntr=0.3,0.1

Type RM Length L Ch R = 1,3199,444,444,444
BEGIN DESCRIPTION:
Stream0371 5.0
END DESCRIPTION:
XS GIS Cut Line= 3
      1852724.99     13994475.01      1852125.00     13995075.00
      1851974.99     13995525.04
#Sta/Elev= 30
  4151.1 2098.39  4235.9 2092.78  4377.4 2087.08  4476.4 2084.56  4716.8 2080.34
  4730.9 2080.59  4773.3 2079.72  4858.2 2079.10  4872.3 2078.47  4886.5 2076.27
  4900.6 2075.54  4914.8 2075.67  4957.2 2073.40  4989.5 2072.61  4990.0 2072.11
  5002.2 2072.11  5002.7 2072.61  5020.7 2073.32  5031.2 2074.96  5052.3 2076.73
  5094.5 2078.14  5231.5 2081.02  5294.8 2083.26  5326.4 2085.36  5358.0 2088.29
  5389.6 2092.55  5431.8 2100.35  5452.9 2102.08  5463.4 2101.32  5474.0 2101.62
#Mann=3,-1,0
  4151.1    0.07       0  4989.5    0.05       0  5002.7    0.07       0
Bank Sta=4989.5,5002.7
Exp/Cntr=0.3,0.1

Type RM Length L Ch R = 1,2755,461,461,461
BEGIN DESCRIPTION:
Stream0371 4.0
END DESCRIPTION:
XS GIS Cut Line= 3
      1852975.01     13994225.00      1851775.00     13994825.00
      1851225.04     13995124.98
#Sta/Elev= 30
  3667.6 2128.97  3752.0 2124.69  3810.2 2120.31  3846.5 2114.48  3913.6 2106.10
  4061.7 2094.57  4123.2 2091.31  4302.1 2085.24  4620.7 2078.41  4822.0 2075.46
  4866.7 2074.25  4897.4 2071.64  4919.8 2072.88  4972.9 2069.56  4995.3 2070.30
  4999.8 2068.69  5000.3 2068.19  5013.2 2068.69  5044.8 2074.20  5134.5 2076.96
  5148.3 2077.97  5164.4 2081.22  5349.5 2087.12  5398.9 2090.55  5458.7 2097.72
  5496.7 2105.23  5533.2 2109.07  5562.2 2115.83  5600.1 2121.34  5635.7 2122.24
#Mann=4,-1,0
  3667.6     0.1       0  3752.0    0.07       0  4999.8    0.05       0
  5013.2    0.07       0
Bank Sta=4999.8,5013.2
Exp/Cntr=0.3,0.1

Type RM Length L Ch R = 1,2294,455,455,455
BEGIN DESCRIPTION:
Stream0371 3.0
END DESCRIPTION:
XS GIS Cut Line= 3
      1852825.00     13994175.00      1851625.00     13994475.00
      1851425.03     13994624.98
#Sta/Elev= 30
  3758.5 2120.92  3781.7 2118.98  3830.7 2111.29  3882.2 2106.20  4098.7 2093.31
  4106.4 2092.30  4111.5 2092.65  4170.8 2089.39  4181.1 2088.26  4304.8 2084.04
  4572.8 2078.26  4642.4 2075.64  4724.9 2073.99  4812.5 2073.83  4943.9 2071.63
  4977.4 2070.61  4998.6 2069.06  5002.3 2064.19  5002.8 2063.69  5015.7 2064.19
  5031.9 2065.56  5038.1 2066.85  5045.4 2069.43  5052.7 2070.64  5081.9 2070.71
  5109.0 2071.84  5123.6 2075.04  5138.1 2080.61  5145.4 2081.75  5245.4 2086.03
#Mann=3,-1,0
  3758.5    0.07       0  5002.3    0.05       0  5015.7    0.07       0
Bank Sta=5002.3,5015.7
Exp/Cntr=0.3,0.1

Type RM Length L Ch R = 1,1839,451,451,451
BEGIN DESCRIPTION:
Stream0371 2.0
END DESCRIPTION:
XS GIS Cut Line= 3
      1852510.91     13993872.11      1851475.00     13994075.00
      1851275.00     13994425.00
#Sta/Elev= 30
  3944.8 2108.29  4037.7 2098.53  4089.1 2094.81  4256.5 2086.26  4351.7 2084.41
  4429.7 2081.77  4449.6 2081.63  4501.1 2079.33  4572.4 2078.23  4609.1 2074.25
  4660.6 2072.07  4796.6 2071.03  4871.7 2068.30  4908.7 2068.59  4939.2 2067.99
  4959.6 2069.45  4990.2 2069.45  4997.8 2067.05  5008.3 2066.65  5014.1 2062.75
  5023.4 2063.42  5029.0 2061.97  5029.5 2061.47  5041.9 2061.47  5042.4 2061.97
  5058.0 2065.28  5067.3 2070.48  5073.1 2072.52  5255.9 2079.11  5403.5 2082.64
#Mann=3,-1,0
  3944.8    0.07       0  5029.0    0.05       0  5042.4    0.07       0
Bank Sta=5029,5042.4
Exp/Cntr=0.3,0.1

Type RM Length L Ch R = 1,1388,364,364,364
BEGIN DESCRIPTION:
Stream0371 1.0
END DESCRIPTION:
XS GIS Cut Line= 3
      1852334.30     13993650.09      1851425.00     13993675.00
      1850824.99     13994225.01
#Sta/Elev= 30
  4090.7 2096.77  4400.1 2085.14  4448.9 2084.54  4640.2 2078.53  4840.3 2075.30
  4870.3 2073.08  4910.3 2064.14  4930.3 2065.42  4960.3 2064.15  4970.3 2065.79
  4990.3 2065.43  5003.7 2065.02  5007.4 2063.71  5007.5 2062.36  5008.0 2061.86
  5021.0 2062.36  5064.2 2064.69  5085.1 2064.51  5099.3 2066.60  5149.3 2066.13
  5177.0 2069.12  5198.6 2070.02  5347.2 2071.94  5532.0 2076.18  5533.9 2076.22
  5580.9 2077.60  5658.6 2081.64  5722.1 2083.23  5736.3 2084.68  5814.3 2088.17
#Mann=5,-1,0
  4090.7    0.07       0  5007.5    0.05       0  5021.0    0.07       0
  5532.0   0.035       0  5533.9    0.07       0
Bank Sta=5007.5,5021
Exp/Cntr=0.3,0.1