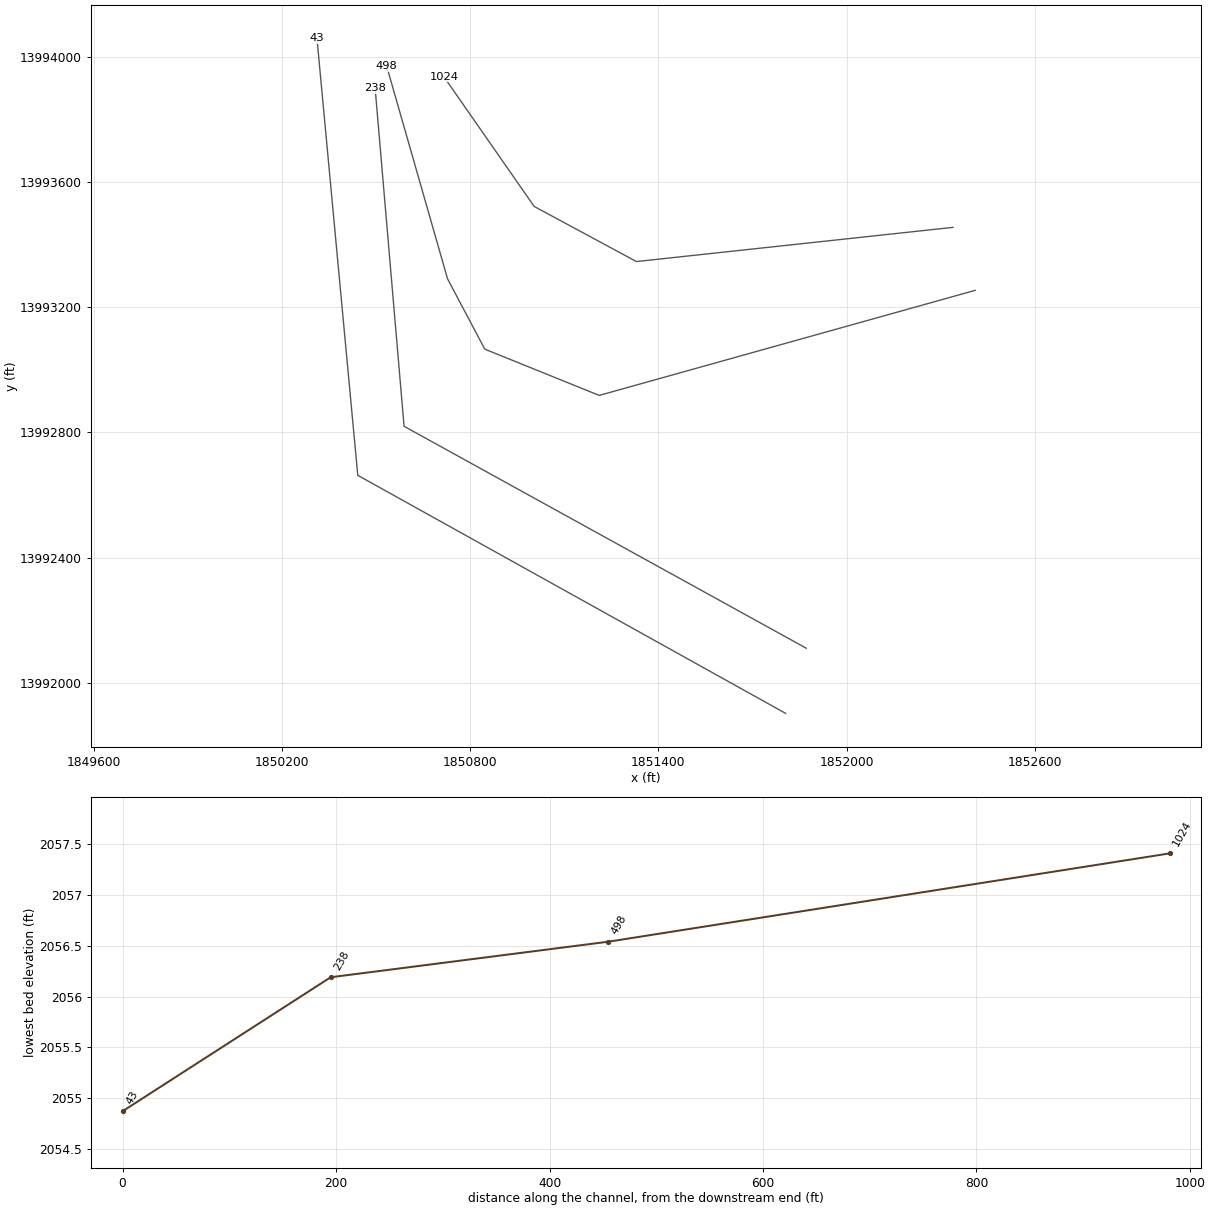
HEC-RAS study Stream0371.prj: Stream0371 Base Level Engineering

--- Stream0371.g01 (geometry) --- (continued)

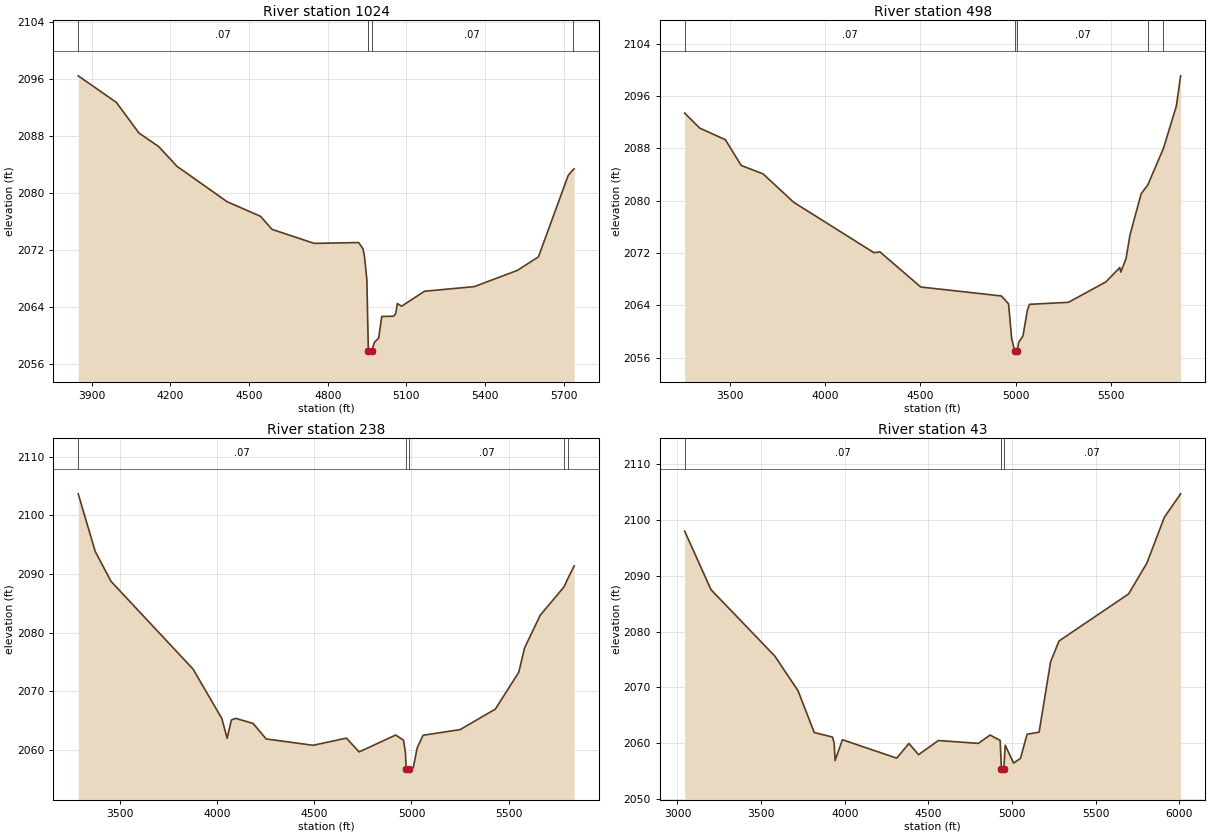
Type RM Length L Ch R = 1,1024,526,526,526
BEGIN DESCRIPTION:
Stream0371 0.1
END DESCRIPTION:
XS GIS Cut Line= 4
      1852339.61     13993455.01      1851329.99     13993345.79
      1851003.91     13993521.88      1850715.63     13993936.63
#Sta/Elev= 30
  3848.6 2096.49  3994.1 2092.76  4080.3 2088.46  4155.0 2086.57  4225.4 2083.78
  4416.5 2078.81  4544.1 2076.76  4587.5 2074.93  4748.4 2072.96  4918.0 2073.08
  4934.2 2072.22  4939.9 2071.25  4949.3 2067.85  4955.0 2057.91  4955.5 2057.41
  4968.5 2057.91  4978.0 2059.07  4994.2 2059.65  5006.2 2062.70  5051.6 2062.73
  5059.8 2063.14  5065.5 2064.52  5081.7 2064.14  5169.3 2066.24  5359.2 2066.89
  5523.3 2069.17  5603.6 2071.07  5717.1 2082.50  5733.5 2083.22  5739.8 2083.42
#Mann=4,-1,0
  3848.6    0.07       0  4955.0    0.05       0  4968.5    0.07       0
  5733.5   0.035       0
Bank Sta=4955,4968.5
Exp/Cntr=0.3,0.1

Type RM Length L Ch R = 1,498,260,260,260
BEGIN DESCRIPTION:
Stream0371 0.0
END DESCRIPTION:
XS GIS Cut Line= 5
      1852410.59     13993253.87      1851211.38     13992918.23
      1850846.39     13993066.02      1850727.62     13993290.68
      1850533.43     13993970.18
#Sta/Elev= 30
  3264.4 2093.37  3342.9 2091.09  3477.9 2089.30  3561.0 2085.37  3675.2 2084.09
  3835.7 2079.75  4256.7 2072.04  4287.9 2072.17  4501.9 2066.80  4924.9 2065.43
  4962.2 2064.23  4978.6 2058.95  4993.8 2057.04  4994.3 2056.54  5007.4 2057.04
  5015.4 2058.32  5038.1 2059.34  5060.7 2063.22  5072.3 2064.15  5276.5 2064.46
  5472.7 2067.58  5545.5 2069.77  5550.7 2069.08  5578.1 2071.13  5598.9 2074.75
  5657.3 2081.04  5692.7 2082.42  5774.5 2088.00  5841.8 2094.44  5864.3 2099.07
#Mann=5,-1,0
  3264.4    0.07       0  4993.8    0.05       0  5007.4    0.07       0
  5692.7   0.035       0  5774.5    0.07       0
Bank Sta=4993.8,5007.4
Exp/Cntr=0.3,0.1

Type RM Length L Ch R = 1,238,195,195,195
BEGIN DESCRIPTION:
Stream0371 0.2
END DESCRIPTION:
XS GIS Cut Line= 3
      1851871.60     13992110.74      1850588.97     13992819.55
      1850496.73     13993898.66
#Sta/Elev= 30
  3287.4 2103.68  3374.9 2093.84  3455.9 2088.75  3877.6 2073.77  4025.3 2065.35
  4052.8 2061.97  4074.5 2065.08  4096.3 2065.37  4186.1 2064.50  4253.3 2061.85
  4494.6 2060.77  4665.7 2061.99  4731.0 2059.64  4918.9 2062.52  4959.1 2061.63
  4969.1 2059.45  4973.0 2056.69  4973.5 2056.19  4986.6 2056.69  5009.2 2056.97
  5029.3 2060.33  5059.4 2062.48  5250.1 2063.45  5430.8 2066.94  5551.2 2073.22
  5581.3 2077.40  5661.6 2082.96  5784.1 2087.81  5804.7 2089.31  5835.9 2091.38
#Mann=5,-1,0
  3287.4    0.07       0  4973.0    0.05       0  4986.6    0.07       0
  5784.1   0.035       0  5804.7    0.07       0
Bank Sta=4973,4986.6
Exp/Cntr=0.3,0.1

Type RM Length L Ch R = 1,43,0,0,0
BEGIN DESCRIPTION:
Stream0371 0.5
END DESCRIPTION:
XS GIS Cut Line= 3
      1851805.91     13991902.59      1850441.33     13992663.00
      1850311.13     13994058.80
#Sta/Elev= 30
  3043.2 2097.94  3200.5 2087.48  3582.3 2075.60  3720.6 2069.42  3817.7 2061.95
  3926.3 2061.14  3936.6 2060.09  3942.3 2056.94  3985.8 2060.66  4310.4 2057.37
  4383.6 2060.00  4440.9 2057.99  4559.6 2060.52  4798.2 2060.01  4868.5 2061.50
  4928.7 2060.53  4936.4 2055.37  4936.9 2054.87  4950.0 2055.37  4958.9 2059.67
  5009.1 2056.48  5050.3 2057.34  5089.4 2061.64  5161.4 2062.01  5230.0 2074.57
  5280.3 2078.30  5696.7 2086.73  5805.8 2092.24  5909.8 2100.41  6007.2 2104.61
#Mann=3,-1,0
  3043.2    0.07       0  4936.4    0.05       0  4950.0    0.07       0
Bank Sta=4936.4,4950
Exp/Cntr=0.3,0.1

Chan Stop Cuts=-1