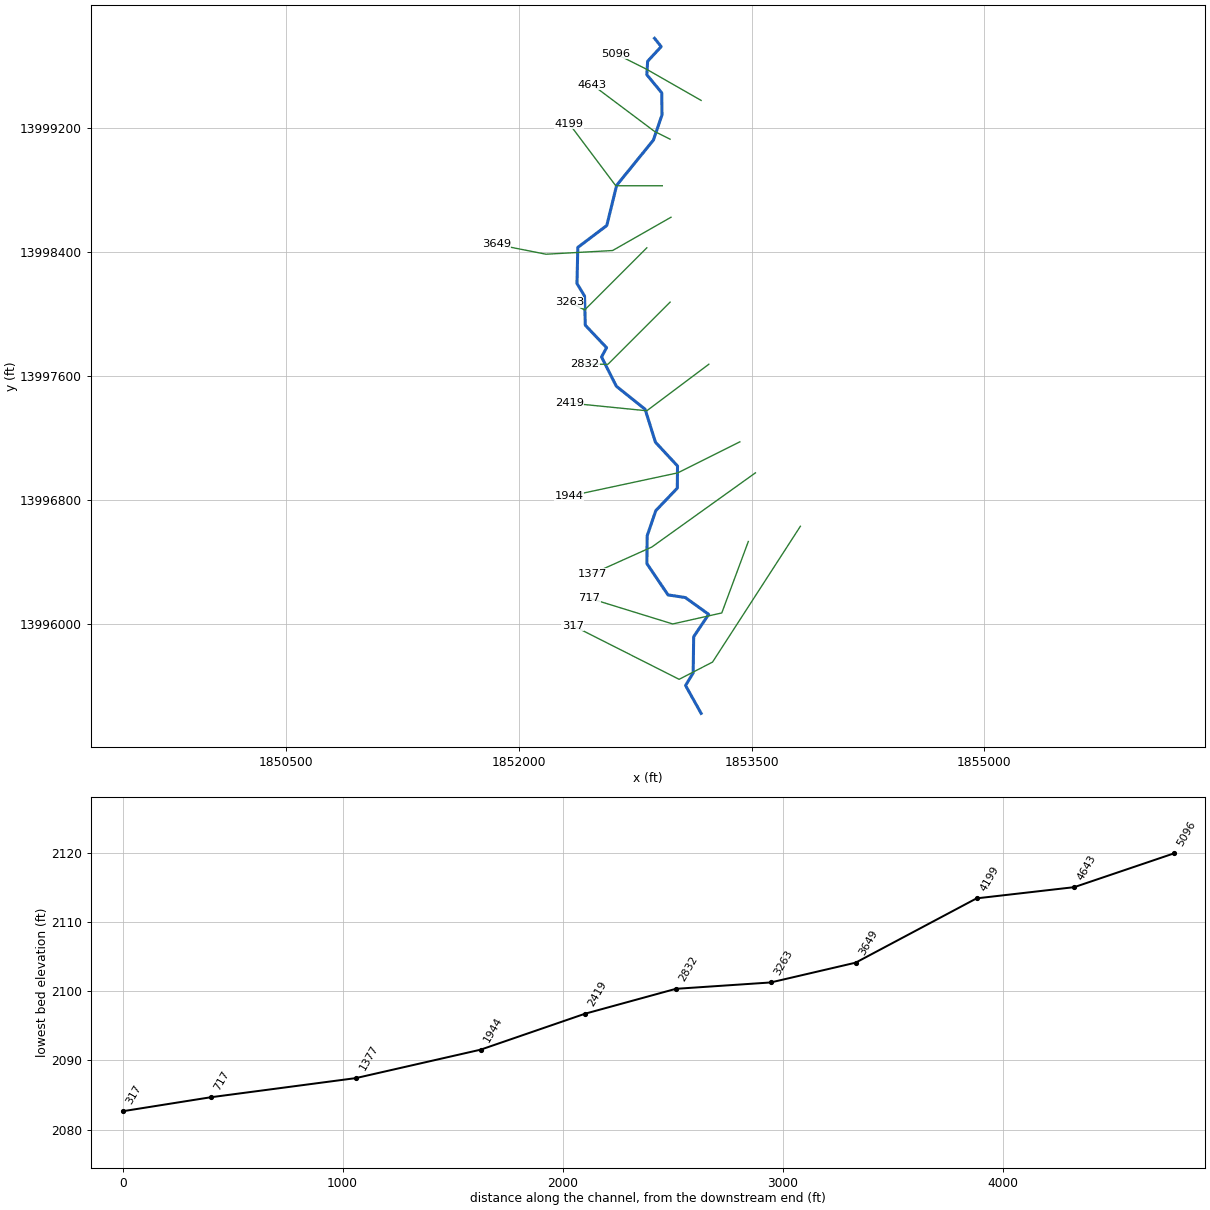
--- Stream0372.prj (project) ---

Proj Title=Stream0372 Base Level Engineering
Current Plan=p01
Default Exp/Contr=0.3,0.1
English Units
Geom File=g01
Flow File=f01
Plan File=p01
BEGIN DESCRIPTION:
Stream0372
END DESCRIPTION:

--- Stream0372.p01 (plan) ---

Plan Title=Multiple Run
Short Identifier=Multiple
Geom File=g01
Flow File=f01
Subcritical Flow
K Sum by GR= 0
Std Step Tol= 0.01
Critical Tol= 0.01
Num of Std Step Trials= 20
Max Error Tol= 0.3
Flow Tol Ratio= 0.001
Split Flow NTrial= 30
Split Flow Tol= 0.02
Split Flow Ratio= 0.02
Log Output Level= 0
Friction Slope Method= 1
Unsteady Friction Slope Method= 2
Unsteady Bridges Friction Slope Method= 1
Parabolic Critical Depth
Global Vel Dist=  1 , 1 , 1
Global Log Level= 0
CheckData=True
Encroach Param= -1, 0, 0, 0
BEGIN DESCRIPTION:
Multiple Run
END DESCRIPTION:

--- Stream0372.f01 (steady flow) ---

Flow Title=Multiple
Number of Profiles=7
Profile Names=10-year,25-year,50-year,1pct_min,100-year,1pct_plu,500-year
River Rch & RM= Stream0372,Reach-1,5096
    1695    2952    4169    2838    5662   11297   10334
Boundary for River Rch & Prof#=Stream0372,Reach-1,1
Up Type=0
Dn Type=3
Dn Slope=0.005
Boundary for River Rch & Prof#=Stream0372,Reach-1,2
Up Type=0
Dn Type=3
Dn Slope=0.005
Boundary for River Rch & Prof#=Stream0372,Reach-1,3
Up Type=0
Dn Type=3
Dn Slope=0.005
Boundary for River Rch & Prof#=Stream0372,Reach-1,4
Up Type=0
Dn Type=3
Dn Slope=0.005
Boundary for River Rch & Prof#=Stream0372,Reach-1,5
Up Type=0
Dn Type=3
Dn Slope=0.005
Boundary for River Rch & Prof#=Stream0372,Reach-1,6
Up Type=0
Dn Type=3
Dn Slope=0.005
Boundary for River Rch & Prof#=Stream0372,Reach-1,7
Up Type=0
Dn Type=3
Dn Slope=0.005

--- Stream0372.g01 (geometry) ---

Geom Title=Existing Conditions

River Reach=Stream0372,Reach-1
Reach XY= 30
      1852875.00     13999775.00      1852917.73     13999721.67
      1852830.42     13999627.43      1852825.24     13999540.22
      1852921.46     13999423.53      1852922.75     13999280.94
      1852867.14     13999118.83      1852630.54     13998827.42
      1852567.15     13998568.81      1852380.36     13998427.70
      1852375.07     13998195.03      1852423.78     13998114.49
      1852428.54     13997926.46      1852565.70     13997781.67
      1852533.25     13997721.77      1852628.51     13997533.48
      1852814.24     13997384.68      1852880.52     13997172.57
      1853022.95     13997019.14      1853021.47     13996876.47
      1852882.86     13996731.17      1852827.26     13996569.06
      1852825.50     13996390.21      1852961.67     13996188.39
      1853073.50     13996171.37      1853223.87     13996062.97
      1853127.07     13995919.15      1853123.76     13995685.50
      1853074.71     13995604.82      1853175.00     13995425.00

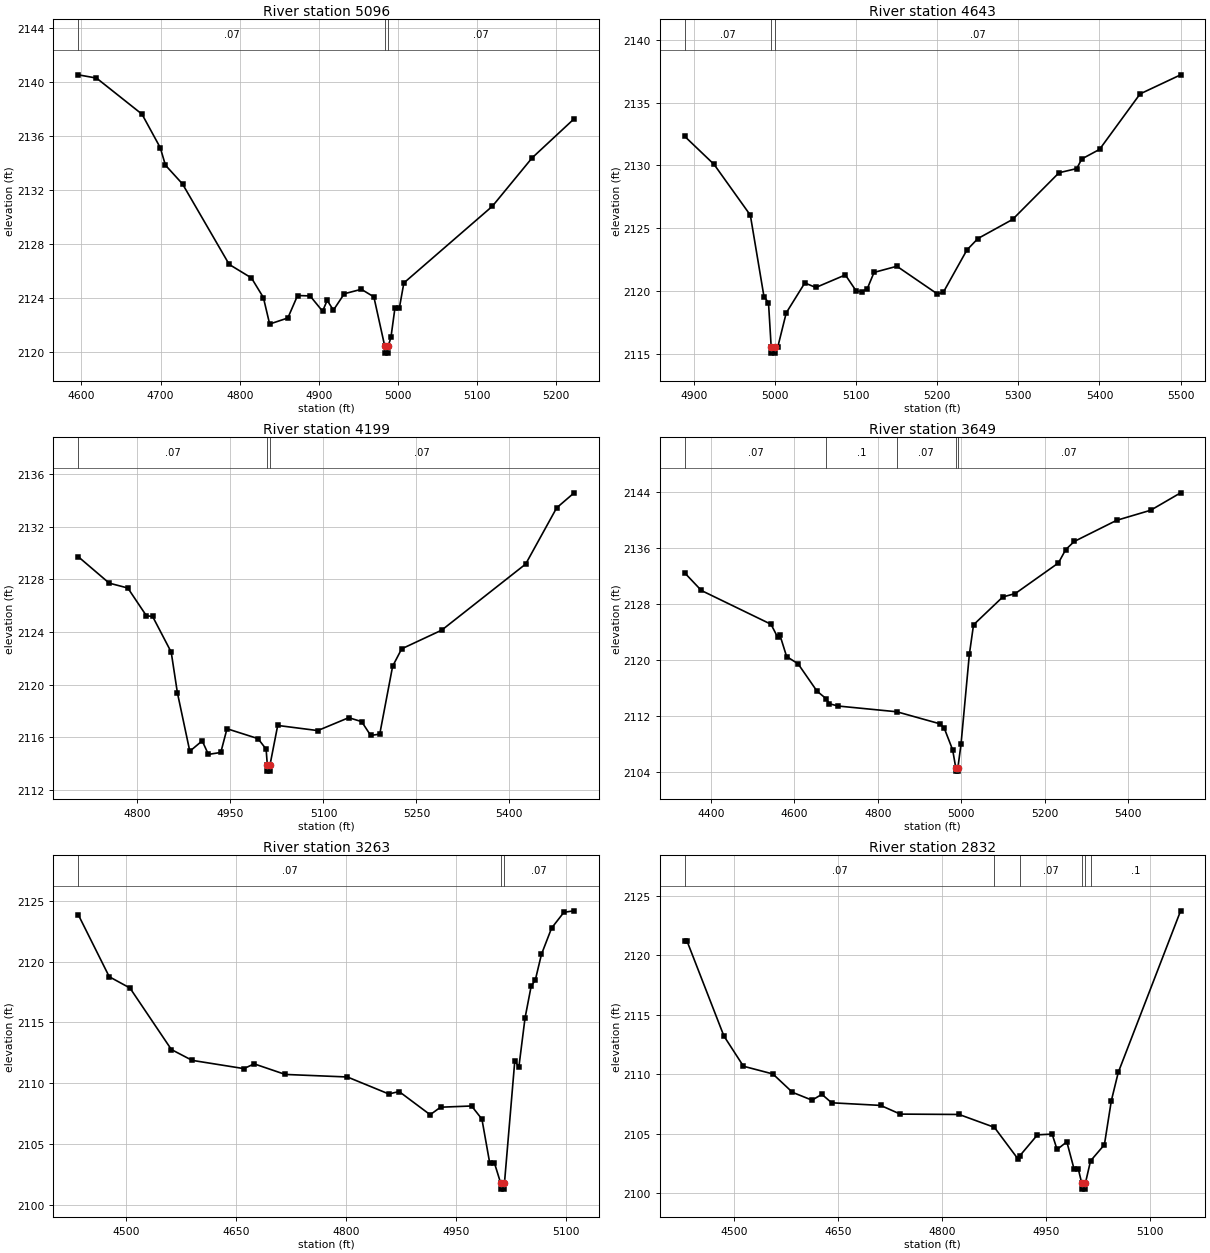
Type RM Length L Ch R = 1,5096,453,453,453
BEGIN DESCRIPTION:
Stream0372 8.0
END DESCRIPTION:
XS GIS Cut Line= 3
      1853175.02     13999374.99      1852825.00     13999575.00
      1852625.04     13999674.98
#Sta/Elev= 30
  4595.9 2140.51  4619.0 2140.27  4676.5 2137.60  4699.6 2135.12  4706.1 2133.83
  4727.7 2132.44  4786.7 2126.49  4814.8 2125.49  4829.9 2124.04  4837.8 2122.08
  4860.8 2122.53  4873.1 2124.19  4888.9 2124.16  4904.7 2123.03  4910.5 2123.83
  4918.4 2123.11  4932.1 2124.32  4953.7 2124.65  4969.5 2124.09  4983.3 2120.43
  4983.5 2119.93  4987.2 2119.93  4987.5 2120.43  4991.1 2121.10  4996.2 2123.29
  5001.8 2123.29  5007.4 2125.12  5119.2 2130.79  5169.5 2134.37  5222.6 2137.26
#Mann=3,-1,0
  4595.9    0.07       0  4983.3    0.05       0  4987.5    0.07       0
Bank Sta=4983.3,4987.5
Exp/Cntr=0.3,0.1

Type RM Length L Ch R = 1,4643,444,444,444
BEGIN DESCRIPTION:
Stream0372 7.0
END DESCRIPTION:
XS GIS Cut Line= 3
      1852974.96     13999125.02      1852875.00     13999175.00
      1852474.97     13999475.02
#Sta/Elev= 30
  4888.3 2132.32  4924.6 2130.08  4969.3 2126.04  4986.1 2119.56  4991.7 2119.07
  4995.0 2115.55  4995.4 2115.05  4999.2 2115.05  4999.5 2115.55  5003.2 2115.55
  5013.6 2118.26  5036.5 2120.64  5050.1 2120.28  5086.5 2121.28  5100.1 2119.98
  5107.4 2119.95  5113.6 2120.19  5121.9 2121.48  5150.1 2121.97  5200.1 2119.76
  5207.4 2119.90  5236.5 2123.27  5250.1 2124.18  5292.8 2125.70  5350.1 2129.42
  5371.9 2129.75  5378.2 2130.52  5400.1 2131.28  5450.1 2135.70  5500.1 2137.22
#Mann=3,-1,0
  4888.3    0.07       0  4995.0    0.05       0  4999.5    0.07       0
Bank Sta=4995,4999.5
Exp/Cntr=0.3,0.1

Type RM Length L Ch R = 1,4199,550,550,550
BEGIN DESCRIPTION:
Stream0372 6.0
END DESCRIPTION:
XS GIS Cut Line= 3
      1852924.95     13998825.00      1852625.00     13998825.00
      1852324.97     13999225.04
#Sta/Elev= 30
  4704.4 2129.72  4754.4 2127.71  4784.4 2127.34  4814.4 2125.23  4824.4 2125.18
  4854.4 2122.47  4864.4 2119.38  4884.4 2114.94  4904.4 2115.73  4914.4 2114.70
  4934.4 2114.85  4944.4 2116.65  4994.4 2115.90  5007.5 2115.10  5009.4 2113.93
  5009.7 2113.43  5013.6 2113.43  5013.9 2113.93  5026.2 2116.90  5090.8 2116.51
  5140.8 2117.49  5161.6 2117.19  5176.2 2116.14  5190.8 2116.24  5211.6 2121.40
  5226.2 2122.72  5290.8 2124.14  5426.2 2129.16  5476.2 2133.43  5504.4 2134.57
#Mann=3,-1,0
  4704.4    0.07       0  5009.4    0.05       0  5013.9    0.07       0
Bank Sta=5009.4,5013.9
Exp/Cntr=0.3,0.1

Type RM Length L Ch R = 1,3649,386,386,386
BEGIN DESCRIPTION:
Stream0372 5.1
END DESCRIPTION:
XS GIS Cut Line= 4
      1852980.88     13998622.05      1852604.78     13998407.68
      1852175.67     13998383.81      1851854.54     13998447.19
#Sta/Elev= 30
  4336.5 2132.49  4376.5 2129.97  4543.6 2125.14  4559.5 2123.30  4565.2 2123.56
  4581.1 2120.52  4608.5 2119.49  4654.0 2115.57  4675.8 2114.50  4683.4 2113.77
  4705.0 2113.44  4845.6 2112.62  4949.5 2110.89  4959.5 2110.25  4979.5 2107.17
  4986.9 2104.63  4987.3 2104.13  4991.7 2104.13  4992.1 2104.63  4999.5 2107.94
  5019.6 2120.85  5029.6 2125.06  5099.7 2129.04  5129.7 2129.53  5233.3 2133.91
  5250.8 2135.82  5271.2 2136.98  5373.1 2140.01  5454.7 2141.45  5526.5 2143.94
#Mann=5,-1,0
  4336.5    0.07       0  4675.8     0.1       0  4845.6    0.07       0
  4986.9    0.05       0  4992.1    0.07       0
Bank Sta=4986.9,4992.1
Exp/Cntr=0.3,0.1

Type RM Length L Ch R = 1,3263,431,431,431
BEGIN DESCRIPTION:
Stream0372 5.0
END DESCRIPTION:
XS GIS Cut Line= 3
      1852825.00     13998425.00      1852425.00     13998025.00
      1852324.99     13998075.01
#Sta/Elev= 30
  4434.3 2123.89  4476.7 2118.77  4505.0 2117.84  4561.6 2112.77  4589.9 2111.88
  4660.6 2111.20  4674.7 2111.59  4717.1 2110.72  4802.0 2110.51  4858.6 2109.11
  4872.7 2109.31  4915.1 2107.40  4929.3 2108.02  4971.7 2108.12  4985.8 2107.04
  4996.4 2103.44  5002.8 2103.44  5011.4 2101.77  5011.8 2101.27  5016.2 2101.27
  5016.6 2101.77  5030.7 2111.83  5036.3 2111.34  5044.7 2115.37  5053.1 2118.00
  5058.7 2118.49  5067.1 2120.61  5081.0 2122.78  5097.8 2124.08  5111.8 2124.20
#Mann=3,-1,0
  4434.3    0.07       0  5011.4    0.05       0  5016.6    0.07       0
Bank Sta=5011.4,5016.6
Exp/Cntr=0.3,0.1

Type RM Length L Ch R = 1,2832,413,413,413
BEGIN DESCRIPTION:
Stream0372 4.0
END DESCRIPTION:
XS GIS Cut Line= 3
      1852974.99     13998074.99      1852575.00     13997675.00
      1852424.97     13997675.00
#Sta/Elev= 30
  4429.1 2121.16  4432.6 2121.16  4485.7 2113.21  4513.9 2110.67  4556.4 2110.02
  4584.6 2108.48  4612.9 2107.82  4627.1 2108.31  4641.2 2107.60  4711.9 2107.38
  4740.2 2106.65  4825.1 2106.62  4876.0 2105.54  4909.9 2102.90  4912.6 2103.14
  4938.2 2104.91  4959.4 2104.97  4966.5 2103.68  4980.6 2104.32  4991.2 2102.00
  4997.3 2102.00  5002.1 2100.85  5002.5 2100.35  5007.0 2100.35  5007.4 2100.85
  5014.8 2102.72  5034.8 2104.08  5044.8 2107.77  5054.8 2110.15  5144.8 2123.72
#Mann=6,-1,0
  4429.1    0.07       0  4876.0     0.1       0  4912.6    0.07       0
  5002.1    0.05       0  5007.4    0.07       0  5014.8     0.1       0
Bank Sta=5002.1,5007.4
Exp/Cntr=0.3,0.1

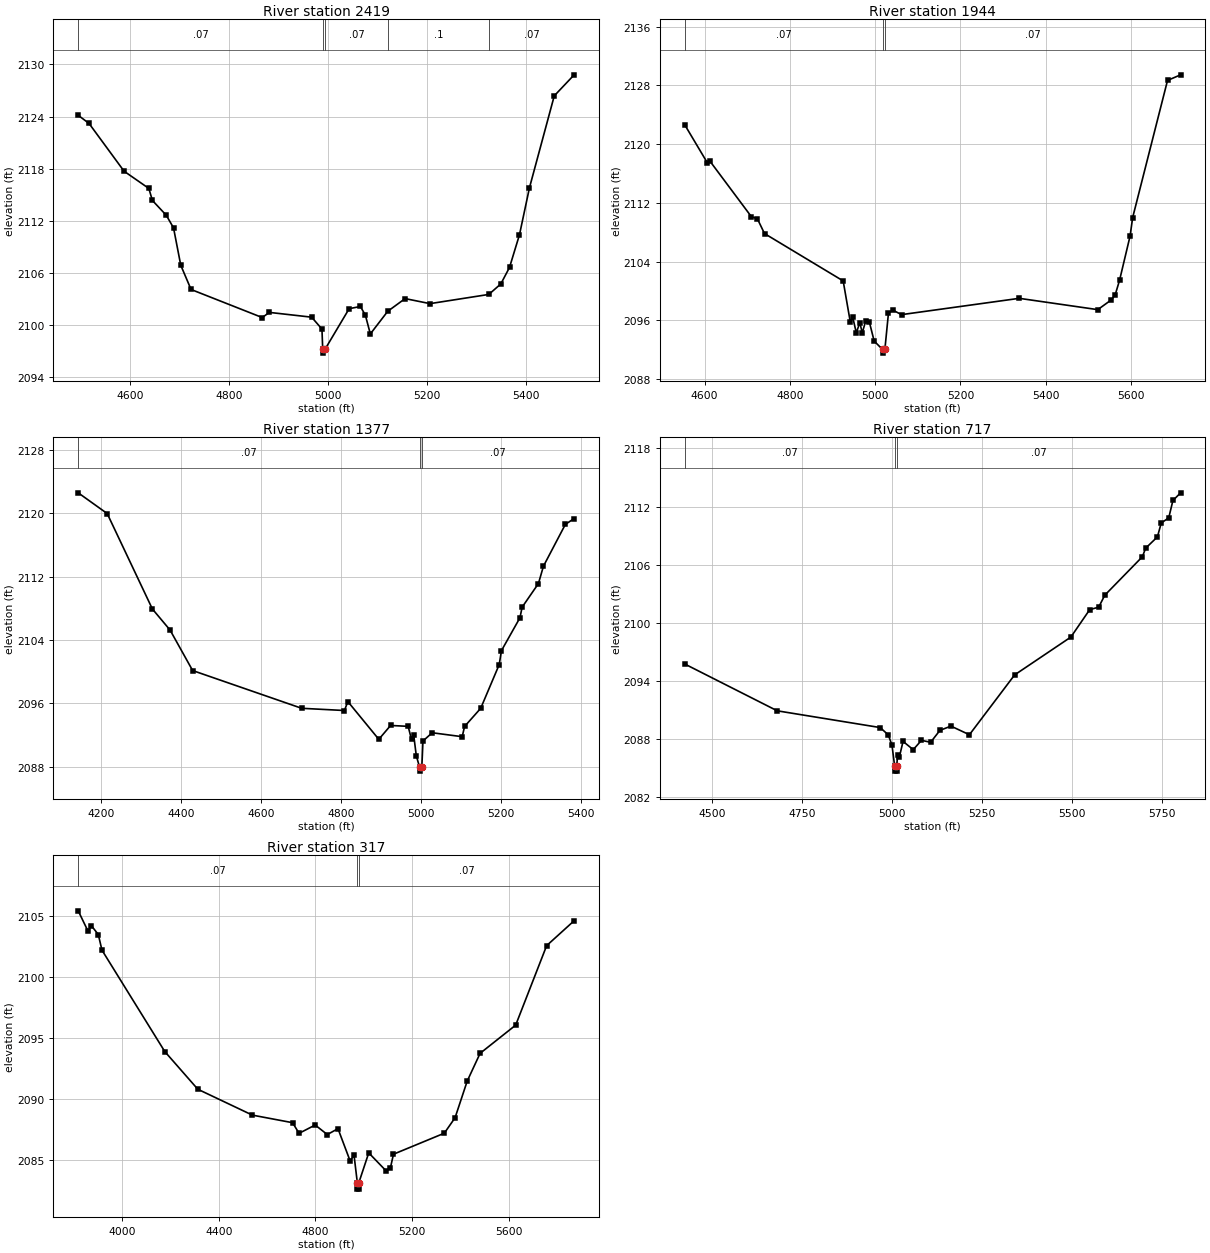
Type RM Length L Ch R = 1,2419,475,475,475
BEGIN DESCRIPTION:
Stream0372 3.0
END DESCRIPTION:
XS GIS Cut Line= 3
      1853225.01     13997675.01      1852825.00     13997375.00
      1852325.00     13997425.00
#Sta/Elev= 30
  4495.0 2124.14  4516.9 2123.20  4587.7 2117.70  4637.7 2115.72  4645.0 2114.33
  4673.1 2112.62  4687.7 2111.17  4702.3 2106.87  4723.1 2104.08  4866.9 2100.85
  4881.5 2101.44  4966.9 2100.89  4987.7 2099.52  4989.2 2097.25  4989.6 2096.75
  4994.5 2097.25  5042.7 2101.87  5065.4 2102.12  5075.4 2101.13  5085.5 2098.96
  5120.7 2101.57  5155.8 2103.03  5206.1 2102.45  5325.0 2103.51  5349.3 2104.72
  5366.9 2106.63  5387.0 2110.39  5407.1 2115.78  5457.3 2126.38  5497.5 2128.80
#Mann=5,-1,0
  4495.0    0.07       0  4989.2    0.05       0  4994.5    0.07       0
  5120.7     0.1       0  5325.0    0.07       0
Bank Sta=4989.2,4994.5
Exp/Cntr=0.3,0.1

Type RM Length L Ch R = 1,1944,567,567,567
BEGIN DESCRIPTION:
Stream0372 2.0
END DESCRIPTION:
XS GIS Cut Line= 3
      1853424.97     13997174.98      1853025.00     13996975.00
      1852324.97     13996824.99
#Sta/Elev= 30
  4553.4 2122.65  4606.5 2117.47  4612.1 2117.73  4709.9 2110.12  4723.9 2109.84
  4740.6 2107.83  4925.1 2101.38  4941.9 2095.76  4947.5 2096.43  4955.9 2094.32
  4964.2 2095.70  4969.8 2094.31  4978.2 2095.97  4986.6 2095.76  4997.8 2093.19
  5017.4 2092.05  5017.8 2091.55  5022.9 2092.05  5031.3 2097.00  5041.5 2097.41
  5061.9 2096.79  5338.1 2099.01  5522.2 2097.47  5553.7 2098.79  5563.1 2099.50
  5573.3 2101.47  5598.0 2107.50  5604.0 2110.00  5685.8 2128.68  5716.5 2129.44
#Mann=3,-1,0
  4553.4    0.07       0  5017.4    0.05       0  5022.9    0.07       0
Bank Sta=5017.4,5022.9
Exp/Cntr=0.3,0.1

Type RM Length L Ch R = 1,1377,660,660,660
BEGIN DESCRIPTION:
Stream0372 1.0
END DESCRIPTION:
XS GIS Cut Line= 3
      1853524.99     13996974.99      1852857.35     13996496.94
      1852474.98     13996324.99
#Sta/Elev= 30
  4143.2 2122.61  4215.7 2119.99  4328.7 2107.93  4372.9 2105.27  4429.4 2100.15
  4702.1 2095.38  4809.0 2095.10  4817.6 2096.23  4895.0 2091.46  4924.5 2093.21
  4968.4 2093.10  4976.8 2091.44  4982.3 2091.98  4988.8 2089.38  4997.0 2087.94
  4997.5 2087.44  5002.6 2087.94  5005.5 2091.25  5028.6 2092.29  5103.6 2091.79
  5109.5 2093.08  5149.9 2095.38  5196.2 2100.91  5201.7 2102.66  5248.0 2106.82
  5253.5 2108.16  5294.3 2111.15  5306.8 2113.34  5361.6 2118.62  5383.6 2119.36
#Mann=3,-1,0
  4143.2    0.07       0  4997.0    0.05       0  5002.6    0.07       0
Bank Sta=4997,5002.6
Exp/Cntr=0.3,0.1

Type RM Length L Ch R = 1,717,400,400,400
BEGIN DESCRIPTION:
Stream0372 0.0
END DESCRIPTION:
XS GIS Cut Line= 4
      1853479.17     13996532.61      1853308.11     13996072.19
      1852991.97     13996001.20      1852453.46     13996167.55
#Sta/Elev= 30
  4424.1 2095.74  4681.5 2090.90  4967.7 2089.17  4990.2 2088.41  5000.4 2087.36
  5007.9 2085.17  5008.3 2084.67  5013.0 2084.67  5013.5 2085.17  5016.2 2086.37
  5021.3 2086.18  5031.2 2087.74  5059.5 2086.89  5082.4 2087.85  5107.9 2087.65
  5133.7 2088.88  5164.4 2089.32  5215.7 2088.43  5341.4 2094.61  5497.8 2098.52
  5550.1 2101.35  5575.2 2101.61  5592.0 2102.84  5696.6 2106.82  5705.7 2107.70
  5738.4 2108.87  5749.0 2110.30  5769.9 2110.84  5781.5 2112.63  5802.9 2113.42
#Mann=3,-1,0
  4424.1    0.07       0  5007.9    0.05       0  5013.5    0.07       0
Bank Sta=5007.9,5013.5
Exp/Cntr=0.3,0.1

Type RM Length L Ch R = 1,317,0,0,0
BEGIN DESCRIPTION:
Stream0372 0.1
END DESCRIPTION:
XS GIS Cut Line= 4
      1853814.61     13996630.62      1853248.62     13995755.60
      1853033.34     13995644.49      1852347.53     13995990.86
#Sta/Elev= 30
  3818.3 2105.44  3859.2 2103.76  3872.6 2104.23  3901.4 2103.50  3916.6 2102.22
  4176.5 2093.92  4313.3 2090.83  4539.2 2088.71  4705.5 2088.09  4732.5 2087.22
  4799.1 2087.90  4849.2 2087.12  4893.5 2087.60  4943.5 2084.97  4960.0 2085.42
  4973.7 2083.15  4974.2 2082.65  4978.9 2082.65  4979.4 2083.15  5020.8 2085.62
  5092.9 2084.14  5110.7 2084.41  5123.2 2085.51  5333.6 2087.23  5378.2 2088.50
  5428.4 2091.50  5481.7 2093.77  5629.0 2096.08  5757.2 2102.59  5871.0 2104.63
#Mann=3,-1,0
  3818.3    0.07       0  4973.7    0.05       0  4979.4    0.07       0
Bank Sta=4973.7,4979.4
Exp/Cntr=0.3,0.1

Chan Stop Cuts=-1