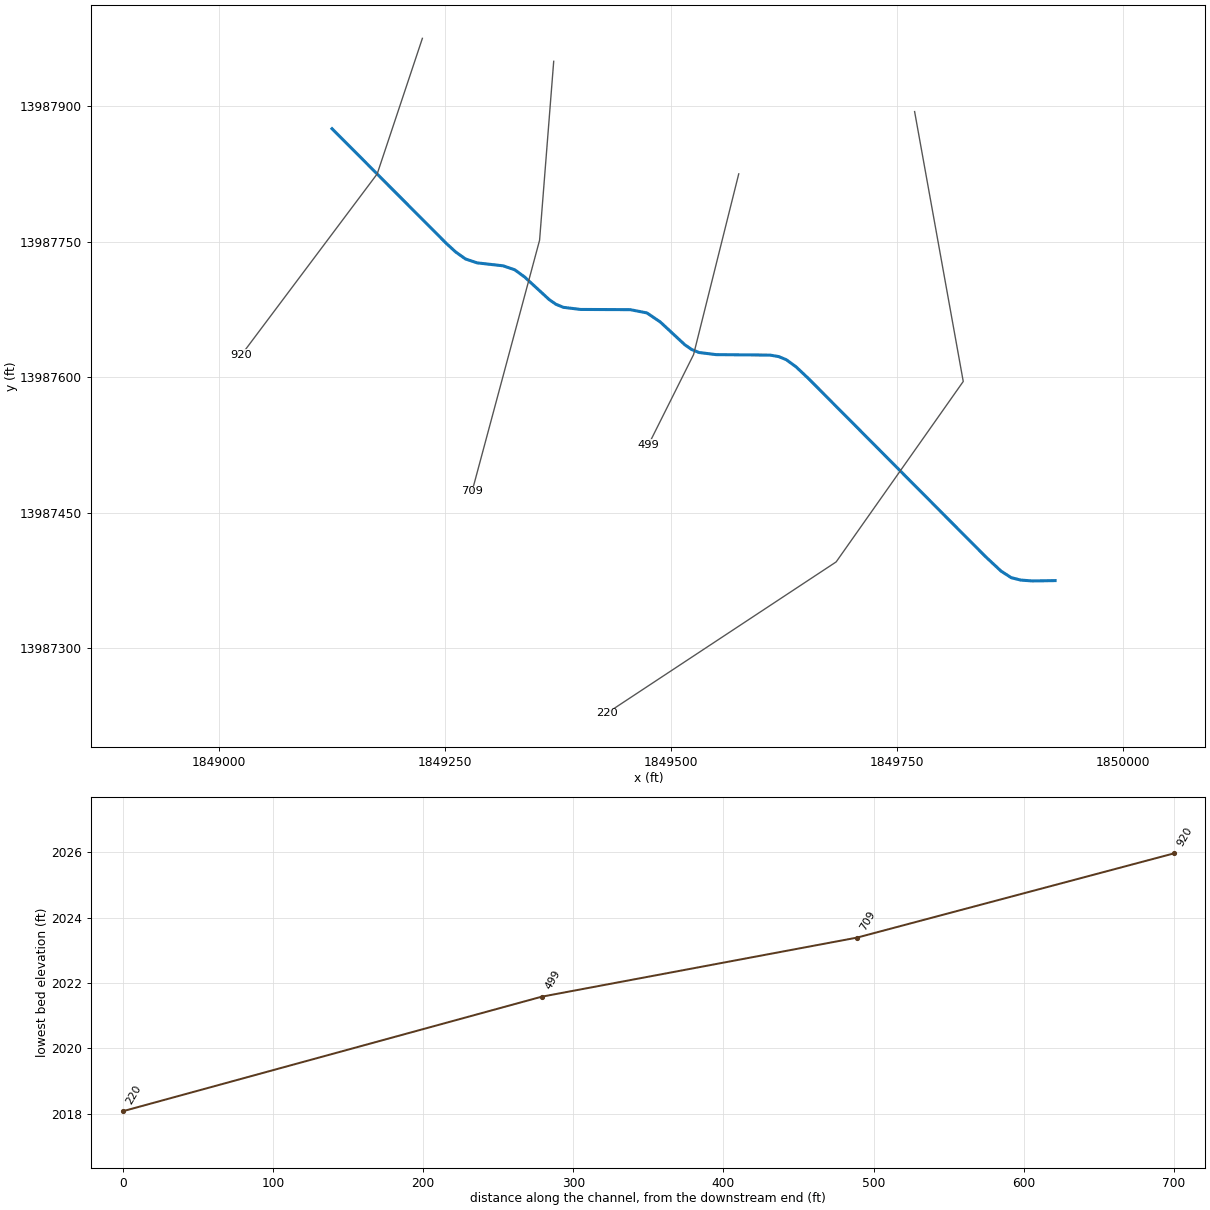
--- Stream0378.prj (project) ---

Proj Title=Stream0378 Base Level Engineering
Current Plan=p01
Default Exp/Contr=0.3,0.1
English Units
Geom File=g01
Flow File=f01
Plan File=p01
BEGIN DESCRIPTION:
Stream0378
END DESCRIPTION:

--- Stream0378.p01 (plan) ---

Plan Title=Multiple Run
Short Identifier=Multiple
Geom File=g01
Flow File=f01
Subcritical Flow
K Sum by GR= 0
Std Step Tol= 0.01
Critical Tol= 0.01
Num of Std Step Trials= 20
Max Error Tol= 0.3
Flow Tol Ratio= 0.001
Split Flow NTrial= 30
Split Flow Tol= 0.02
Split Flow Ratio= 0.02
Log Output Level= 0
Friction Slope Method= 1
Unsteady Friction Slope Method= 2
Unsteady Bridges Friction Slope Method= 1
Parabolic Critical Depth
Global Vel Dist=  1 , 1 , 1
Global Log Level= 0
CheckData=True
Encroach Param= -1, 0, 0, 0
BEGIN DESCRIPTION:
Multiple Run
END DESCRIPTION:

--- Stream0378.f01 (steady flow) ---

Flow Title=Multiple
Number of Profiles=7
Profile Names=10-year,25-year,50-year,1pct_min,100-year,1pct_plu,500-year
River Rch & RM= Stream0378,Reach-1,920
    1069    1818    2527    1696    3384    6753    6001
Boundary for River Rch & Prof#=Stream0378,Reach-1,1
Up Type=0
Dn Type=3
Dn Slope=0.005
Boundary for River Rch & Prof#=Stream0378,Reach-1,2
Up Type=0
Dn Type=3
Dn Slope=0.005
Boundary for River Rch & Prof#=Stream0378,Reach-1,3
Up Type=0
Dn Type=3
Dn Slope=0.005
Boundary for River Rch & Prof#=Stream0378,Reach-1,4
Up Type=0
Dn Type=3
Dn Slope=0.005
Boundary for River Rch & Prof#=Stream0378,Reach-1,5
Up Type=0
Dn Type=3
Dn Slope=0.005
Boundary for River Rch & Prof#=Stream0378,Reach-1,6
Up Type=0
Dn Type=3
Dn Slope=0.005
Boundary for River Rch & Prof#=Stream0378,Reach-1,7
Up Type=0
Dn Type=3
Dn Slope=0.005

--- Stream0378.g01 (geometry) ---

Geom Title=Existing Conditions

River Reach=Stream0378,Reach-1
Reach XY= 30
      1849125.00     13987875.00      1849251.53     13987748.00
      1849261.78     13987738.61      1849272.70     13987730.83
      1849285.62     13987726.50      1849314.29     13987723.28
      1849327.17     13987718.86      1849338.04     13987710.95
      1849365.35     13987685.84      1849372.68     13987680.77
      1849380.97     13987677.33      1849400.00     13987674.99
      1849454.90     13987674.76      1849473.40     13987671.15
      1849488.13     13987661.18      1849515.37     13987635.89
      1849522.69     13987630.81      1849530.98     13987627.36
      1849550.00     13987625.01      1849609.78     13987624.48
      1849619.11     13987622.85      1849627.43     13987619.48
      1849638.30     13987611.60      1849651.87     13987598.82
      1849848.20     13987401.35      1849865.21     13987385.51
      1849876.36     13987378.27      1849886.84     13987375.59
      1849899.63     13987374.59      1849925.00     13987375.00

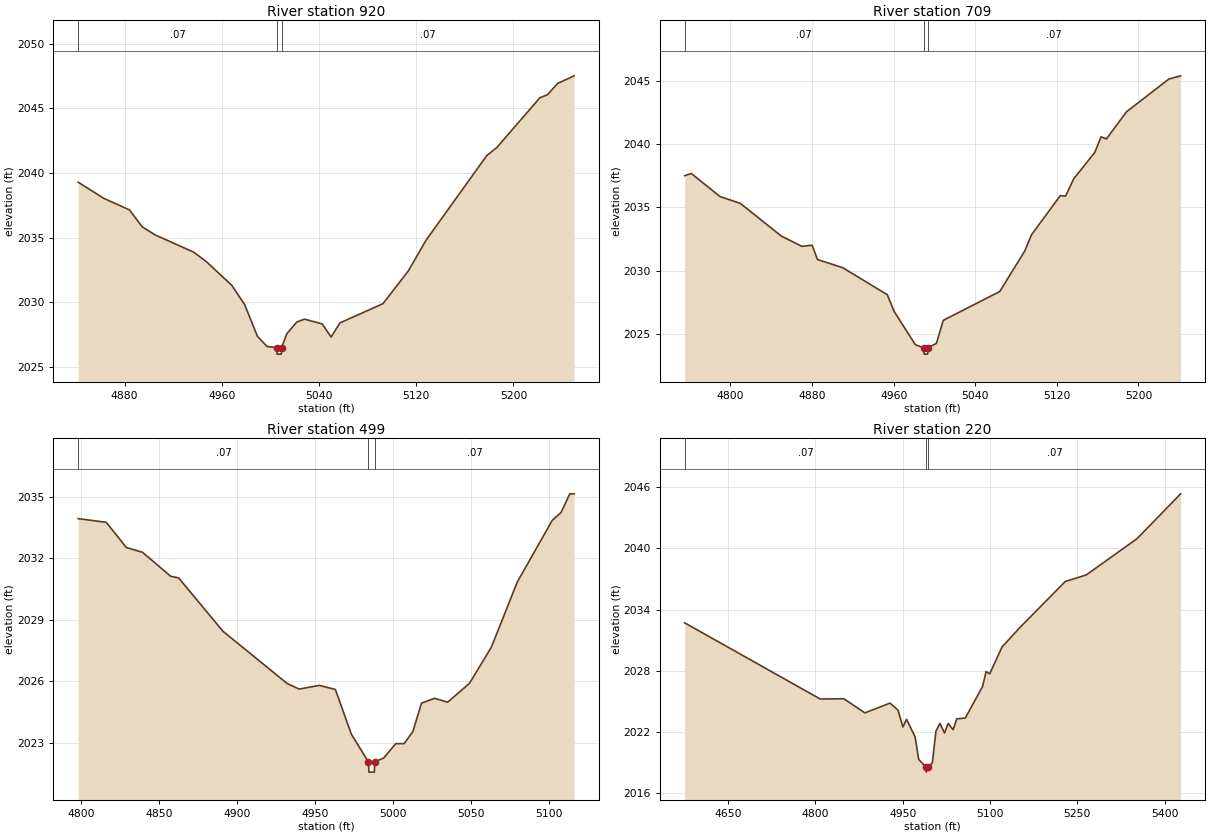
Type RM Length L Ch R = 1,920,211,211,211
BEGIN DESCRIPTION:
Stream0378 2.0
END DESCRIPTION:
XS GIS Cut Line= 3
      1849224.98     13987974.95      1849175.00     13987825.00
      1849024.98     13987624.97
#Sta/Elev= 30
  4841.9 2039.29  4862.9 2038.04  4884.0 2037.15  4894.6 2035.83  4905.1 2035.21
  4936.7 2033.88  4947.3 2033.14  4968.3 2031.30  4978.9 2029.80  4989.4 2027.35
  4997.3 2026.56  5005.3 2026.47  5005.5 2025.97  5009.0 2025.97  5009.3 2026.47
  5013.5 2027.54  5021.8 2028.46  5028.1 2028.68  5042.7 2028.31  5050.0 2027.29
  5057.3 2028.39  5092.7 2029.88  5113.5 2032.41  5128.1 2034.79  5178.1 2041.35
  5186.4 2041.98  5221.8 2045.83  5228.1 2046.07  5236.4 2046.94  5250.0 2047.53
#Mann=3,-1,0
  4841.9    0.07       0  5005.3    0.05       0  5009.3    0.07       0
Bank Sta=5005.3,5009.3
Exp/Cntr=0.3,0.1

Type RM Length L Ch R = 1,709,210,210,210
BEGIN DESCRIPTION:
Stream0378 3.0
END DESCRIPTION:
XS GIS Cut Line= 3
      1849370.27     13987949.53      1849354.64     13987751.57
      1849279.99     13987473.80
#Sta/Elev= 30
  4755.1 2037.49  4761.6 2037.67  4789.7 2035.85  4809.8 2035.30  4849.9 2032.72
  4870.0 2031.91  4880.0 2032.00  4885.3 2030.87  4910.1 2030.22  4953.7 2028.09
  4960.5 2026.76  4981.2 2024.14  4989.5 2023.89  4989.8 2023.39  4993.3 2023.39
  4993.5 2023.89  5001.9 2024.24  5008.6 2026.06  5064.0 2028.34  5088.5 2031.54
  5095.1 2032.82  5123.3 2035.92  5128.5 2035.88  5136.5 2037.25  5157.2 2039.34
  5163.3 2040.57  5168.5 2040.40  5188.3 2042.55  5229.7 2045.13  5241.3 2045.39
#Mann=3,-1,0
  4755.1    0.07       0  4989.5    0.05       0  4993.5    0.07       0
Bank Sta=4989.5,4993.5
Exp/Cntr=0.3,0.1

Type RM Length L Ch R = 1,499,279,279,279
BEGIN DESCRIPTION:
Stream0378 1.0
END DESCRIPTION:
XS GIS Cut Line= 3
      1849575.00     13987825.01      1849525.00     13987625.00
      1849474.99     13987524.97
#Sta/Elev= 30
  4798.1 2033.94  4816.1 2033.76  4829.0 2032.53  4839.3 2032.30  4857.4 2031.13
  4862.5 2031.05  4890.9 2028.45  4932.1 2025.90  4939.8 2025.63  4952.7 2025.81
  4963.0 2025.61  4973.3 2023.42  4984.2 2022.08  4984.5 2021.58  4988.0 2021.58
  4988.2 2022.08  4994.0 2022.27  5001.7 2022.97  5007.1 2022.97  5012.7 2023.56
  5018.2 2024.94  5026.6 2025.18  5035.0 2024.99  5049.0 2025.91  5063.0 2027.67
  5079.7 2030.86  5102.1 2033.86  5107.7 2034.24  5113.3 2035.15  5116.1 2035.15
#Mann=3,-1,0
  4798.1    0.07       0  4984.2    0.05       0  4988.2    0.07       0
Bank Sta=4984.2,4988.2
Exp/Cntr=0.3,0.1

Type RM Length L Ch R = 1,220,0,0,0
BEGIN DESCRIPTION:
Stream0378 0.0
END DESCRIPTION:
XS GIS Cut Line= 4
      1849769.57     13987893.93      1849823.39     13987595.32
      1849682.77     13987395.67      1849428.81     13987228.09
#Sta/Elev= 30
  4575.5 2032.71  4808.3 2025.24  4848.8 2025.27  4885.1 2023.88  4928.2 2024.84
  4941.8 2024.16  4950.4 2022.50  4956.6 2023.25  4971.4 2021.52  4977.5 2019.31
  4990.3 2018.57  4990.5 2018.07  4994.3 2018.57  5000.9 2019.00  5007.1 2022.07
  5013.9 2022.85  5021.9 2021.90  5028.0 2022.84  5036.7 2022.23  5042.8 2023.29
  5057.6 2023.38  5087.2 2026.47  5093.3 2027.93  5099.5 2027.71  5120.5 2030.33
  5151.0 2032.23  5229.2 2036.76  5265.4 2037.41  5352.7 2040.97  5427.4 2045.36
#Mann=3,-1,0
  4575.5    0.07       0  4990.3    0.05       0  4994.3    0.07       0
Bank Sta=4990.3,4994.3
Exp/Cntr=0.3,0.1

Chan Stop Cuts=-1