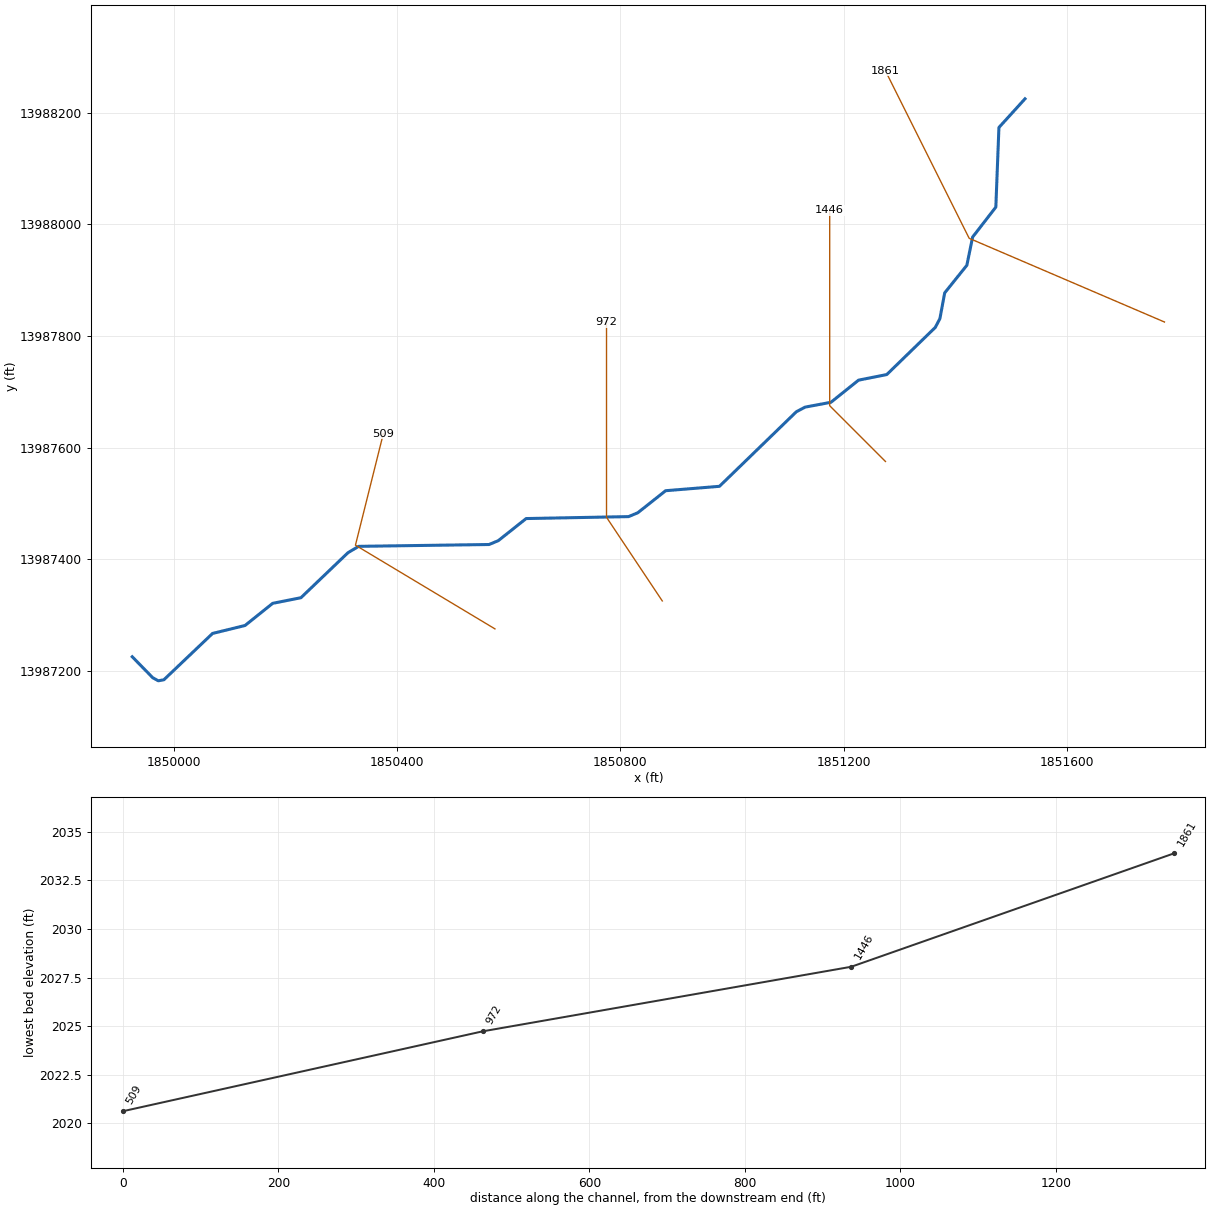
--- Stream0379.prj (project) ---

Proj Title=Stream0379 Base Level Engineering
Current Plan=p01
Default Exp/Contr=0.3,0.1
English Units
Geom File=g01
Flow File=f01
Plan File=p01
BEGIN DESCRIPTION:
Stream0379
END DESCRIPTION:

--- Stream0379.p01 (plan) ---

Plan Title=Multiple Run
Short Identifier=Multiple
Geom File=g01
Flow File=f01
Subcritical Flow
K Sum by GR= 0
Std Step Tol= 0.01
Critical Tol= 0.01
Num of Std Step Trials= 20
Max Error Tol= 0.3
Flow Tol Ratio= 0.001
Split Flow NTrial= 30
Split Flow Tol= 0.02
Split Flow Ratio= 0.02
Log Output Level= 0
Friction Slope Method= 1
Unsteady Friction Slope Method= 2
Unsteady Bridges Friction Slope Method= 1
Parabolic Critical Depth
Global Vel Dist=  1 , 1 , 1
Global Log Level= 0
CheckData=True
Encroach Param= -1, 0, 0, 0
BEGIN DESCRIPTION:
Multiple Run
END DESCRIPTION:

--- Stream0379.f01 (steady flow) ---

Flow Title=Multiple
Number of Profiles=7
Profile Names=10-year,25-year,50-year,1pct_min,100-year,1pct_plu,500-year
River Rch & RM= Stream0379,Reach-1,1861
    1146    1955    2723    1831    3654    7290    6504
Boundary for River Rch & Prof#=Stream0379,Reach-1,1
Up Type=0
Dn Type=3
Dn Slope=0.005
Boundary for River Rch & Prof#=Stream0379,Reach-1,2
Up Type=0
Dn Type=3
Dn Slope=0.005
Boundary for River Rch & Prof#=Stream0379,Reach-1,3
Up Type=0
Dn Type=3
Dn Slope=0.005
Boundary for River Rch & Prof#=Stream0379,Reach-1,4
Up Type=0
Dn Type=3
Dn Slope=0.005
Boundary for River Rch & Prof#=Stream0379,Reach-1,5
Up Type=0
Dn Type=3
Dn Slope=0.005
Boundary for River Rch & Prof#=Stream0379,Reach-1,6
Up Type=0
Dn Type=3
Dn Slope=0.005
Boundary for River Rch & Prof#=Stream0379,Reach-1,7
Up Type=0
Dn Type=3
Dn Slope=0.005

--- Stream0379.g01 (geometry) ---

Geom Title=Existing Conditions

River Reach=Stream0379,Reach-1
Reach XY= 30
      1851525.00     13988225.00      1851478.30     13988173.63
      1851472.76     13988030.93      1851431.12     13987977.18
      1851420.84     13987926.72      1851381.10     13987877.18
      1851372.50     13987831.03      1851364.24     13987815.30
      1851277.31     13987730.83      1851226.74     13987720.81
      1851177.19     13987681.10      1851131.04     13987672.50
      1851115.32     13987664.23      1850977.43     13987530.52
      1850880.98     13987522.64      1850831.06     13987483.14
      1850814.50     13987476.22      1850630.94     13987472.74
      1850581.06     13987433.14      1850564.50     13987426.22
      1850330.86     13987422.94      1850311.69     13987411.60
      1850227.29     13987330.85      1850176.73     13987320.81
      1850127.19     13987281.10      1850068.94     13987266.83
      1849981.66     13987183.79      1849971.66     13987181.96
      1849961.66     13987187.51      1849925.00     13987225.00

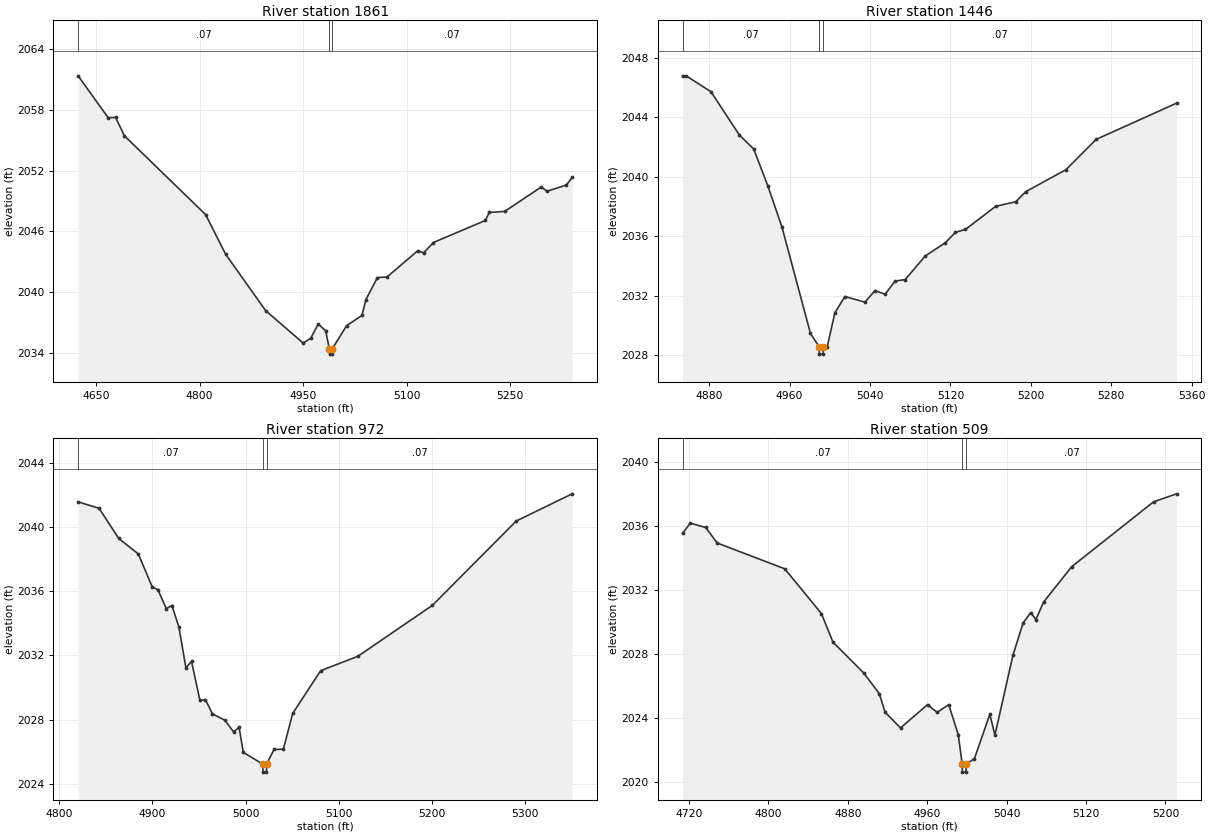
Type RM Length L Ch R = 1,1861,415,415,415
BEGIN DESCRIPTION:
Stream0379 4.0
END DESCRIPTION:
XS GIS Cut Line= 3
      1851774.96     13987825.02      1851425.00     13987975.00
      1851274.98     13988275.04
#Sta/Elev= 30
  4623.8 2061.35  4667.3 2057.22  4678.2 2057.24  4690.8 2055.44  4808.7 2047.65
  4837.7 2043.74  4895.7 2038.18  4950.1 2034.98  4961.0 2035.45  4971.9 2036.86
  4982.8 2036.18  4988.0 2034.39  4988.3 2033.89  4991.8 2033.89  4992.0 2034.39
  5012.9 2036.69  5035.3 2037.71  5040.9 2039.26  5057.6 2041.44  5071.6 2041.50
  5116.3 2044.10  5124.7 2043.88  5138.7 2044.90  5214.2 2047.08  5219.8 2047.87
  5242.1 2047.97  5295.2 2050.38  5303.6 2049.96  5331.6 2050.58  5340.0 2051.32
#Mann=3,-1,0
  4623.8    0.07       0  4988.0    0.05       0  4992.0    0.07       0
Bank Sta=4988,4992
Exp/Cntr=0.3,0.1

Type RM Length L Ch R = 1,1446,474,474,474
BEGIN DESCRIPTION:
Stream0379 3.0
END DESCRIPTION:
XS GIS Cut Line= 3
      1851275.03     13987574.97      1851175.00     13987675.00
      1851175.00     13988025.04
#Sta/Elev= 30
  4853.5 2046.80  4857.1 2046.80  4881.8 2045.73  4910.1 2042.81  4924.3 2041.87
  4938.4 2039.39  4952.5 2036.60  4980.8 2029.45  4989.4 2028.56  4989.7 2028.06
  4993.2 2028.06  4993.4 2028.56  4997.5 2028.56  5005.0 2030.83  5015.0 2031.94
  5035.0 2031.56  5045.0 2032.34  5055.0 2032.09  5065.0 2032.98  5075.0 2033.08
  5095.0 2034.67  5115.0 2035.56  5125.0 2036.26  5135.0 2036.46  5165.0 2038.01
  5185.0 2038.32  5195.0 2039.00  5235.0 2040.48  5265.0 2042.52  5345.0 2044.96
#Mann=3,-1,0
  4853.5    0.07       0  4989.4    0.05       0  4993.4    0.07       0
Bank Sta=4989.4,4993.4
Exp/Cntr=0.3,0.1

Type RM Length L Ch R = 1,972,463,463,463
BEGIN DESCRIPTION:
Stream0379 2.0
END DESCRIPTION:
XS GIS Cut Line= 3
      1850875.00     13987325.00      1850775.00     13987475.00
      1850775.00     13987825.02
#Sta/Elev= 30
  4820.2 2041.56  4842.7 2041.16  4863.8 2039.28  4884.8 2038.32  4899.8 2036.26
  4905.8 2036.10  4914.8 2034.92  4920.9 2035.11  4928.4 2033.76  4935.9 2031.23
  4941.9 2031.64  4950.9 2029.21  4956.9 2029.24  4964.4 2028.37  4977.9 2027.96
  4987.0 2027.25  4993.0 2027.52  4997.5 2025.97  5018.4 2025.24  5018.7 2024.74
  5022.3 2024.74  5022.5 2025.24  5030.5 2026.15  5040.5 2026.17  5050.5 2028.39
  5080.5 2031.05  5120.5 2031.95  5200.5 2035.12  5290.5 2040.37  5350.5 2042.06
#Mann=3,-1,0
  4820.2    0.07       0  5018.4    0.05       0  5022.5    0.07       0
Bank Sta=5018.4,5022.5
Exp/Cntr=0.3,0.1

Type RM Length L Ch R = 1,509,0,0,0
BEGIN DESCRIPTION:
Stream0379 1.0
END DESCRIPTION:
XS GIS Cut Line= 3
      1850574.98     13987275.01      1850325.00     13987425.00
      1850375.00     13987625.02
#Sta/Elev= 30
  4713.5 2035.53  4721.3 2036.17  4736.8 2035.90  4748.5 2034.93  4816.5 2033.32
  4853.4 2030.53  4865.1 2028.74  4896.2 2026.81  4911.7 2025.53  4917.6 2024.37
  4933.1 2023.39  4960.3 2024.84  4970.0 2024.36  4981.7 2024.84  4991.4 2022.94
  4995.2 2021.13  4995.5 2020.63  4999.1 2020.63  4999.3 2021.13  5007.6 2021.48
  5023.1 2024.24  5028.2 2022.94  5046.3 2027.91  5056.6 2029.94  5064.3 2030.59
  5069.5 2030.15  5077.2 2031.24  5105.5 2033.45  5188.0 2037.50  5211.2 2038.00
#Mann=3,-1,0
  4713.5    0.07       0  4995.2    0.05       0  4999.3    0.07       0
Bank Sta=4995.2,4999.3
Exp/Cntr=0.3,0.1

Chan Stop Cuts=-1