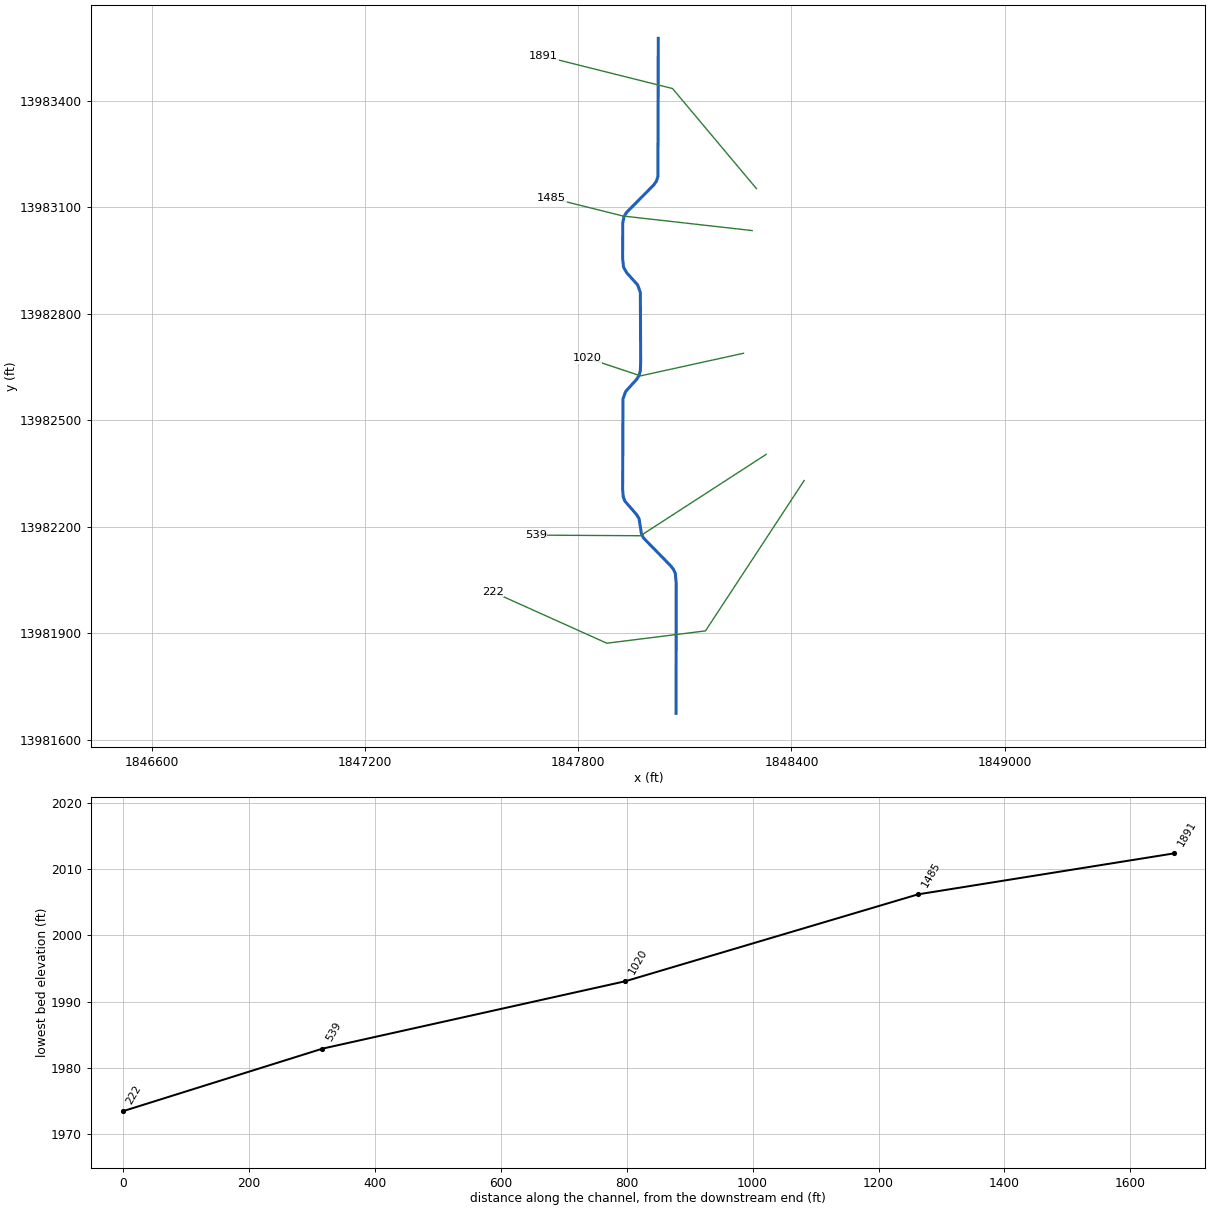
--- Stream0380.prj (project) ---

Proj Title=Stream0380 Base Level Engineering
Current Plan=p01
Default Exp/Contr=0.3,0.1
English Units
Geom File=g01
Flow File=f01
Plan File=p01
Y Axis Title=Elevation
X Axis Title(PF)=Main Channel Distance
X Axis Title(XS)=Station
BEGIN DESCRIPTION:
Stream0380
END DESCRIPTION:
DSS Export Rating Curves= 0
DSS Export Rating Curve Sorted= 0
DSS Export Volume Flow Curves= 0
DXF OffsetX= 0
DXF OffsetY= 0
DXF ScaleX= 1
DXF ScaleY= 10

--- Stream0380.p01 (plan) ---

Plan Title=Multiple Run
Short Identifier=Multiple
Geom File=g01
Flow File=f01
Subcritical Flow
K Sum by GR= 0
Std Step Tol= 0.01
Critical Tol= 0.01
Num of Std Step Trials= 20
Max Error Tol= 0.3
Flow Tol Ratio= 0.001
Split Flow NTrial= 30
Split Flow Tol= 0.02
Split Flow Ratio= 0.02
Log Output Level= 0
Friction Slope Method= 1
Unsteady Friction Slope Method= 2
Unsteady Bridges Friction Slope Method= 1
Parabolic Critical Depth
Global Vel Dist=  1 , 1 , 1
Global Log Level= 0
CheckData=True
Encroach Param= -1, 0, 0, 0
BEGIN DESCRIPTION:
Multiple Run
END DESCRIPTION:

--- Stream0380.f01 (steady flow) ---

Flow Title=Multiple
Program Version=4.10
Number of Profiles= 7
Profile Names=10-year,25-year,50-year,1pct_min,100-year,1pct_plu,500-year
River Rch & RM=Stream0380,Reach-1         ,1891
     532     869    1176     771    1538    3069    2598
Boundary for River Rch & Prof#=Stream0380,Reach-1         , 1
Up Type= 0
Dn Type= 3
Dn Slope=0.02
Boundary for River Rch & Prof#=Stream0380,Reach-1         , 2
Up Type= 0
Dn Type= 3
Dn Slope=0.02
Boundary for River Rch & Prof#=Stream0380,Reach-1         , 3
Up Type= 0
Dn Type= 3
Dn Slope=0.02
Boundary for River Rch & Prof#=Stream0380,Reach-1         , 4
Up Type= 0
Dn Type= 3
Dn Slope=0.02
Boundary for River Rch & Prof#=Stream0380,Reach-1         , 5
Up Type= 0
Dn Type= 3
Dn Slope=0.02
Boundary for River Rch & Prof#=Stream0380,Reach-1         , 6
Up Type= 0
Dn Type= 3
Dn Slope=0.02
Boundary for River Rch & Prof#=Stream0380,Reach-1         , 7
Up Type= 0
Dn Type= 3
Dn Slope=0.02
DSS Import GetInterval= 0
DSS Import GetPeak= 0
DSS Import FillOption= 0

--- Stream0380.g01 (geometry) ---

Geom Title=Existing Conditions
Program Version=4.10

River Reach=Stream0380      ,Reach-1
Reach XY= 30
        1848025.       13983575.      1848023.94     13983185.44
      1848019.52     13983172.55       1848011.6     13983161.69
       1847935.5     13983084.79      1847928.54     13983073.53
      1847924.94     13983055.01      1847924.61     13982954.87
      1847927.25     13982930.94      1847935.85     13982915.36
      1847966.86     13982881.06      1847974.48     13982859.78
      1847975.45     13982664.81      1847974.48     13982640.22
      1847971.22     13982626.57      1847964.15     13982615.35
      1847933.14     13982581.06      1847925.52     13982559.78
      1847924.64     13982304.85       1847926.2      13982285.5
      1847930.71     13982272.65      1847963.84     13982234.52
      1847970.78     13982223.25       1847977.5     13982181.04
      1847983.16     13982168.95      1848058.54     13982091.75
      1848067.17     13982081.19      1848072.94     13982069.14
      1848075.49      13982040.2        1848075.       13981675.

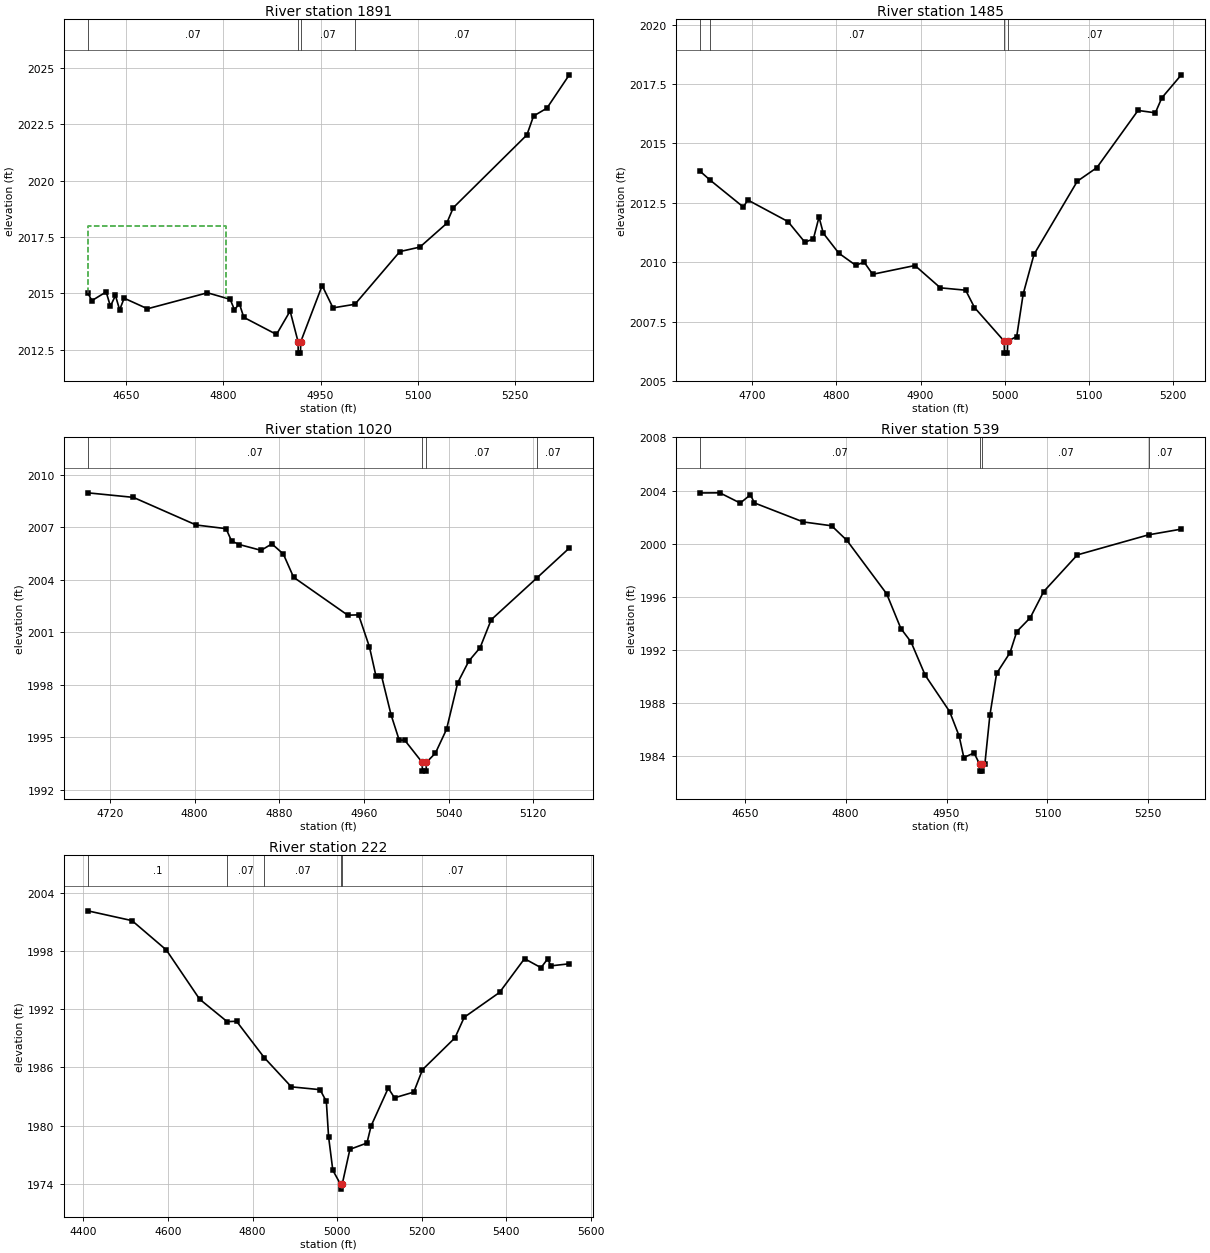
Type RM Length L Ch R = 1 ,1891    ,406,406,406
BEGIN DESCRIPTION:
Stream0380 4.0
END DESCRIPTION:
XS GIS Cut Line= 3
      1848301.37     13983152.02      1848065.09     13983433.74
      1847701.57     13983524.62
#Sta/Elev= 30
    4591 2015.02  4597.3 2014.67  4619.4 2015.06  4625.9 2014.42  4633.7  2014.9
  4640.2 2014.26  4647.1 2014.78  4683.1 2014.31  4775.5 2015.02  4810.6 2014.73
  4817.1 2014.27  4824.9 2014.53  4831.5 2013.93    4882 2013.17    4903 2014.21
  4915.3 2012.84  4915.5 2012.34    4919 2012.34  4919.3 2012.84  4952.4 2015.34
  4969.1 2014.35  5002.9 2014.51  5072.2 2016.85  5103.1 2017.05  5144.3  2018.1
  5154.6  2018.8    5268 2022.03  5278.3 2022.87  5298.9 2023.22  5333.4  2024.7
#Mann= 4 ,-1 , 0
    4591     .07       0  4915.3     .05       0  4919.3     .07       0
  5002.9     .07       0
#XS Ineff= 2 , 0
         4804.26 2017.97
Permanent Ineff=
       F       F
Bank Sta=4915.3,4919.3
XS Rating Curve= 0 ,0
Exp/Cntr=0.3,0.1

Type RM Length L Ch R = 1 ,1485    ,465,465,465
BEGIN DESCRIPTION:
Stream0380 3.0
END DESCRIPTION:
XS GIS Cut Line= 3
      1848289.26     13983033.91        1847925.       13983075.
      1847725.02     13983124.99
#Sta/Elev= 30
  4637.5 2013.84    4650 2013.45  4689.4 2012.32  4694.5 2012.62  4742.4 2011.71
  4762.5 2010.84  4772.6 2010.98  4779.3  2011.9  4784.4 2011.22  4802.8 2010.38
  4822.9 2009.87    4833    2010  4843.1 2009.49  4893.4 2009.86  4923.6 2008.92
  4953.7 2008.82  4964.2 2008.09  4999.6 2006.67  4999.8 2006.17  5003.3 2006.17
  5003.6 2006.67  5014.4 2006.87  5022.1 2008.66    5035 2010.33  5086.5 2013.41
  5109.7 2013.98  5158.7 2016.39  5179.3 2016.29    5187 2016.92  5210.2 2017.89
#Mann= 4 ,-1 , 0
  4637.5    .035       0    4650     .07       0  4999.6     .05       0
  5003.6     .07       0
Bank Sta=4999.6,5003.6
XS Rating Curve= 0 ,0
Exp/Cntr=0.3,0.1

Type RM Length L Ch R = 1 ,1020    ,481,481,481
BEGIN DESCRIPTION:
Stream0380 2.0
END DESCRIPTION:
XS GIS Cut Line= 3
      1848264.98      13982688.6        1847975.       13982625.
      1847824.99       13982675.
#Sta/Elev= 30
    4699 2008.98  4742.1 2008.72  4801.4 2007.14  4829.7 2006.93  4834.9 2006.22
  4842.3 2006.02  4862.8 2005.69    4873 2006.06  4883.8 2005.48  4893.5 2004.15
  4944.7 2001.98  4954.9    2002  4965.2 2000.16  4971.4 1998.48  4976.5 1998.53
  4985.6 1996.28  4993.3 1994.83  4998.5 1994.83    5015 1993.56  5015.2 1993.06
  5018.7 1993.06    5019 1993.56  5027.5 1994.09    5038 1995.45  5048.6 1998.12
  5059.1 1999.36  5069.7 2000.12  5080.2 2001.72  5123.7 2004.13    5154 2005.82
#Mann= 4 ,-1 , 0
    4699     .07       0    5015     .05       0    5019     .07       0
  5123.7     .07       0
Bank Sta=5015,5019
XS Rating Curve= 0 ,0
Exp/Cntr=0.3,0.1

Type RM Length L Ch R = 1 ,539     ,317,317,317
BEGIN DESCRIPTION:
Stream0380 1.0
END DESCRIPTION:
XS GIS Cut Line= 3
       1848328.6     13982403.88        1847975.       13982175.
      1847680.42     13982176.71
#Sta/Elev= 30
  4583.2 2003.82    4613 2003.83  4643.3 2003.06  4658.5 2003.68  4664.4 2003.07
    4737 2001.64  4779.2 2001.35  4801.9 2000.25    4861 1996.23  4882.1 1993.62
  4897.2 1992.61  4918.3  1990.1  4954.6 1987.37  4968.7 1985.53  4975.7 1983.91
  4990.9 1984.26  4999.4 1983.39  4999.7 1982.89  5003.2 1982.89  5003.4 1983.39
  5006.9 1983.39  5014.4 1987.09  5024.4 1990.24  5044.4 1991.81  5054.4 1993.39
  5074.4 1994.43  5094.4  1996.4  5144.4 1999.16  5250.3 2000.67    5299  2001.1
#Mann= 4 ,-1 , 0
  4583.2     .07       0  4999.4     .05       0  5003.4     .07       0
  5250.3     .07       0
Bank Sta=4999.4,5003.4
XS Rating Curve= 0 ,0
Exp/Cntr=0.3,0.1

Type RM Length L Ch R = 1 ,222     ,0,0,0
BEGIN DESCRIPTION:
Stream0380 0.0
END DESCRIPTION:
XS GIS Cut Line= 4
      1848435.67     13982330.33       1848157.9     13981907.17
      1847880.13     13981872.45      1847558.38     13982017.13
#Sta/Elev= 30
  4410.3 2002.13    4515 2001.12  4596.1  1998.1  4674.8 1993.03    4740 1990.71
  4762.2 1990.75  4827.6 1987.01  4891.8 1983.99  4959.7  1983.7  4974.6 1982.49
  4979.9 1978.85  4989.9  1975.4  5008.1 1973.95  5008.4 1973.45  5012.1 1973.95
  5030.3 1977.55  5070.6  1978.2  5080.6 1979.98    5121 1983.86  5135.8 1982.86
  5181.4 1983.45    5202 1985.76  5278.8 1989.04  5300.7 1991.16  5384.2 1993.72
  5443.3  1997.2  5482.3 1996.27  5498.1 1997.18  5505.5 1996.46  5549.2 1996.67
#Mann= 5 ,-1 , 0
  4410.3      .1       0    4740     .07       0  4827.6     .07       0
  5008.1     .05       0  5012.1     .07       0
Bank Sta=5008.1,5012.1
XS Rating Curve= 0 ,0
Exp/Cntr=0.3,0.1

Chan Stop Cuts=-1
Use User Specified Reach Order=0
Composite Channel Slope=5