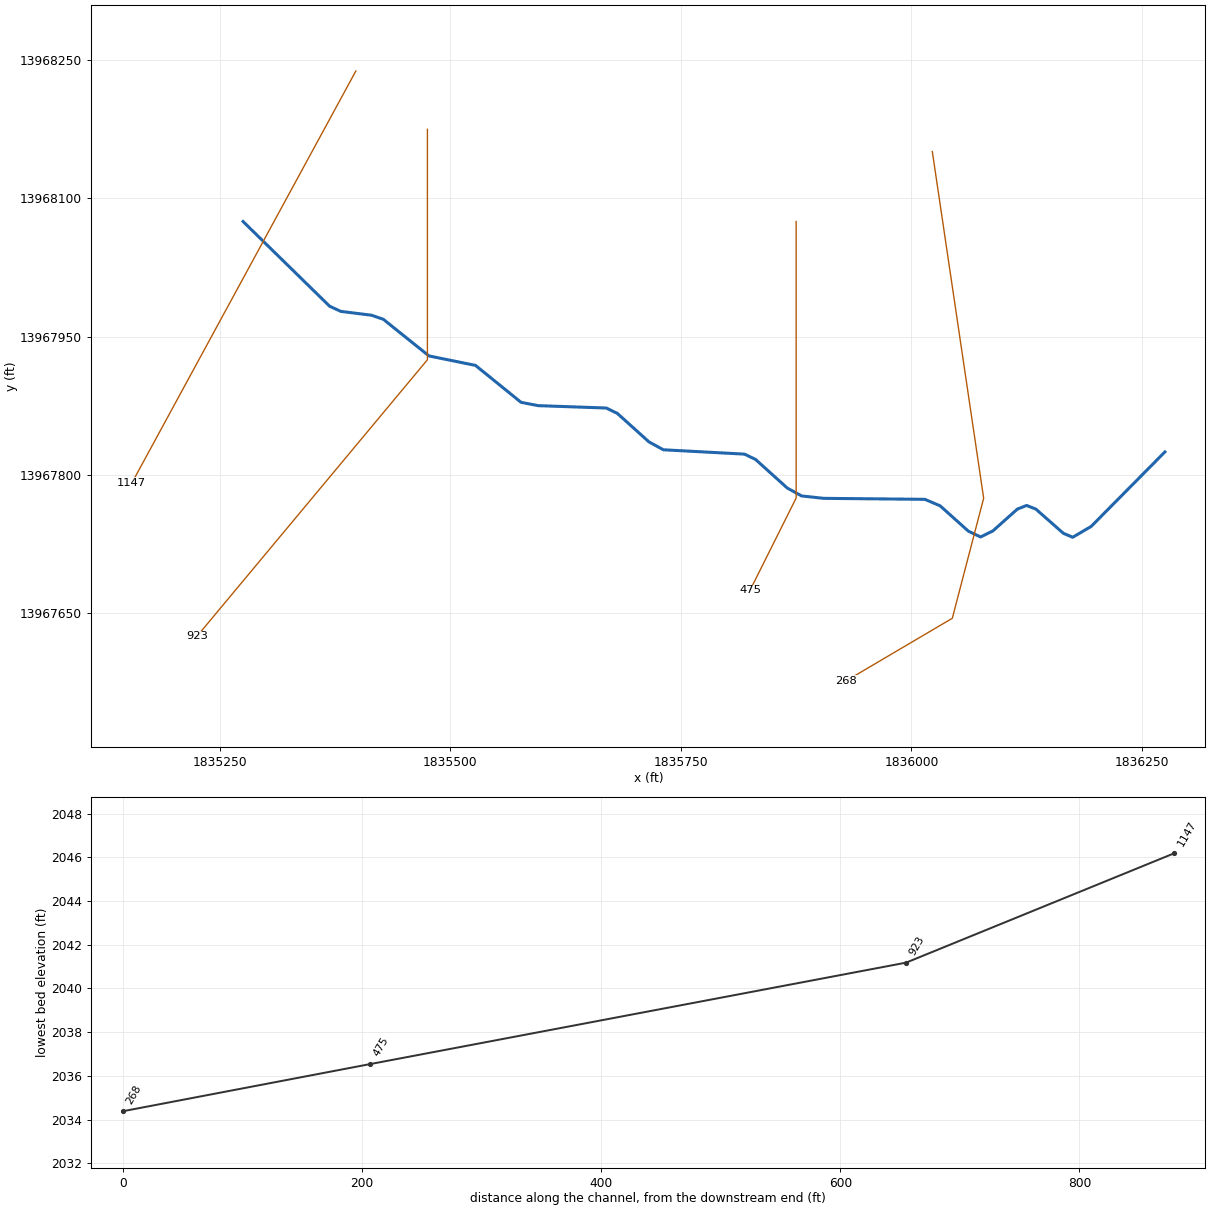
--- Stream0383.prj (project) ---

Proj Title=Stream0383 Base Level Engineering
Current Plan=p01
Default Exp/Contr=0.3,0.1
English Units
Geom File=g01
Flow File=f01
Plan File=p01
BEGIN DESCRIPTION:
Stream0383
END DESCRIPTION:

--- Stream0383.p01 (plan) ---

Plan Title=Multiple Run
Short Identifier=Multiple
Geom File=g01
Flow File=f01
Subcritical Flow
K Sum by GR= 0
Std Step Tol= 0.01
Critical Tol= 0.01
Num of Std Step Trials= 20
Max Error Tol= 0.3
Flow Tol Ratio= 0.001
Split Flow NTrial= 30
Split Flow Tol= 0.02
Split Flow Ratio= 0.02
Log Output Level= 0
Friction Slope Method= 1
Unsteady Friction Slope Method= 2
Unsteady Bridges Friction Slope Method= 1
Parabolic Critical Depth
Global Vel Dist=  1 , 1 , 1
Global Log Level= 0
CheckData=True
Encroach Param= -1, 0, 0, 0
BEGIN DESCRIPTION:
Multiple Run
END DESCRIPTION:

--- Stream0383.f01 (steady flow) ---

Flow Title=Multiple
Number of Profiles=7
Profile Names=10-year,25-year,50-year,1pct_min,100-year,1pct_plu,500-year
River Rch & RM= Stream0383,Reach-1,1147
    1012    1722    2395    1611    3213    6412    5716
Boundary for River Rch & Prof#=Stream0383,Reach-1,1
Up Type=0
Dn Type=3
Dn Slope=0.005
Boundary for River Rch & Prof#=Stream0383,Reach-1,2
Up Type=0
Dn Type=3
Dn Slope=0.005
Boundary for River Rch & Prof#=Stream0383,Reach-1,3
Up Type=0
Dn Type=3
Dn Slope=0.005
Boundary for River Rch & Prof#=Stream0383,Reach-1,4
Up Type=0
Dn Type=3
Dn Slope=0.005
Boundary for River Rch & Prof#=Stream0383,Reach-1,5
Up Type=0
Dn Type=3
Dn Slope=0.005
Boundary for River Rch & Prof#=Stream0383,Reach-1,6
Up Type=0
Dn Type=3
Dn Slope=0.005
Boundary for River Rch & Prof#=Stream0383,Reach-1,7
Up Type=0
Dn Type=3
Dn Slope=0.005

--- Stream0383.g01 (geometry) ---

Geom Title=Existing Conditions

River Reach=Stream0383,Reach-1
Reach XY= 30
      1835275.00     13968075.00      1835368.92     13967983.09
      1835381.03     13967977.48      1835414.30     13967973.32
      1835427.19     13967968.90      1835476.72     13967929.16
      1835527.18     13967918.88      1835576.58     13967878.83
      1835595.09     13967875.23      1835669.03     13967872.65
      1835681.04     13967866.81      1835715.37     13967835.89
      1835730.97     13967827.35      1835819.02     13967822.64
      1835831.03     13967816.81      1835865.35     13967785.85
      1835880.94     13967777.27      1835904.87     13967774.67
      1836014.56     13967773.61      1836031.19     13967766.56
      1836061.84     13967739.06      1836075.10     13967732.78
      1836088.38     13967739.32      1836115.01     13967763.03
      1836125.01     13967766.97      1836135.00     13967763.03
      1836165.00     13967736.65      1836175.00     13967732.46
      1836195.00     13967744.17      1836275.00     13967825.00

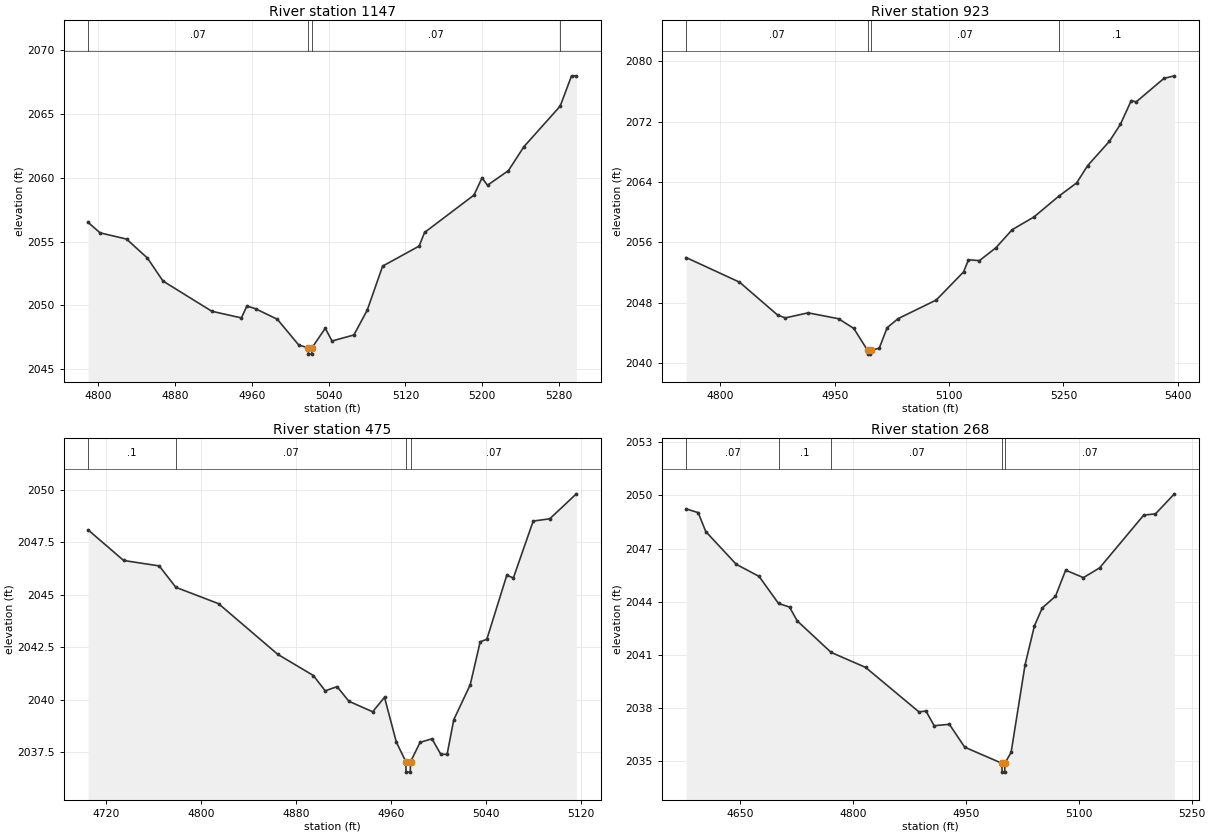
Type RM Length L Ch R = 1,1147,224,224,224
BEGIN DESCRIPTION:
Stream0383 3.0
END DESCRIPTION:
XS GIS Cut Line= 2
      1835397.42     13968238.34      1835154.35     13967791.24
#Sta/Elev= 30
  4789.2 2056.51  4801.7 2055.69  4829.3 2055.20  4851.1 2053.71  4867.3 2051.91
  4918.2 2049.54  4949.0 2049.02  4954.7 2049.95  4963.7 2049.74  4986.5 2048.91
  5008.8 2046.89  5018.6 2046.68  5018.9 2046.18  5022.4 2046.18  5022.6 2046.68
  5036.4 2048.21  5043.4 2047.21  5066.2 2047.68  5080.1 2049.62  5096.2 2053.08
  5134.2 2054.65  5139.9 2055.72  5191.4 2058.65  5199.8 2060.00  5205.5 2059.42
  5227.3 2060.57  5243.5 2062.45  5281.2 2065.62  5293.1 2068.00  5298.1 2068.00
#Mann=4,-1,0
  4789.2    0.07       0  5018.6    0.05       0  5022.6    0.07       0
  5281.2     0.1       0
Bank Sta=5018.6,5022.6
Exp/Cntr=0.3,0.1

Type RM Length L Ch R = 1,923,448,448,448
BEGIN DESCRIPTION:
Stream0383 2.0
END DESCRIPTION:
XS GIS Cut Line= 3
      1835475.00     13968175.00      1835475.00     13967925.00
      1835225.01     13967625.01
#Sta/Elev= 30
  4755.0 2053.98  4825.0 2050.72  4875.0 2046.36  4885.0 2045.98  4915.0 2046.65
  4955.0 2045.87  4975.0 2044.58  4993.0 2041.68  4993.3 2041.18  4996.8 2041.18
  4997.0 2041.68  5008.3 2041.96  5018.7 2044.68  5033.0 2045.88  5083.1 2048.35
  5118.9 2052.07  5125.4 2053.68  5139.7 2053.57  5161.2 2055.26  5182.7 2057.67
  5211.3 2059.36  5243.5 2062.08  5267.3 2063.87  5281.6 2066.15  5310.3 2069.39
  5324.6 2071.62  5338.9 2074.78  5345.4 2074.61  5381.8 2077.72  5395.5 2078.06
#Mann=4,-1,0
  4755.0    0.07       0  4993.0    0.05       0  4997.0    0.07       0
  5243.5     0.1       0
Bank Sta=4993,4997
Exp/Cntr=0.3,0.1

Type RM Length L Ch R = 1,475,207,207,207
BEGIN DESCRIPTION:
Stream0383 1.0
END DESCRIPTION:
XS GIS Cut Line= 3
      1835875.00     13968074.97      1835875.00     13967775.00
      1835824.99     13967674.98
#Sta/Elev= 30
  4704.6 2048.10  4734.6 2046.64  4764.6 2046.38  4778.6 2045.36  4814.6 2044.58
  4864.6 2042.16  4894.6 2041.15  4904.6 2040.42  4914.6 2040.62  4924.6 2039.92
  4944.6 2039.42  4954.6 2040.11  4964.6 2037.97  4972.6 2037.04  4972.8 2036.54
  4976.3 2036.54  4976.6 2037.04  4984.6 2037.96  4994.6 2038.13  5002.1 2037.39
  5007.4 2037.39  5013.0 2039.04  5026.9 2040.71  5035.3 2042.76  5040.9 2042.88
  5057.7 2045.93  5063.3 2045.81  5080.0 2048.52  5094.0 2048.63  5116.4 2049.82
#Mann=4,-1,0
  4704.6     0.1       0  4778.6    0.07       0  4972.6    0.05       0
  4976.6    0.07       0
Bank Sta=4972.6,4976.6
Exp/Cntr=0.3,0.1

Type RM Length L Ch R = 1,268,0,0,0
BEGIN DESCRIPTION:
Stream0383 0.0
END DESCRIPTION:
XS GIS Cut Line= 4
      1836022.71     13968150.86      1836078.41     13967774.80
      1836044.40     13967644.57      1835929.26     13967576.75
#Sta/Elev= 30
  4578.6 2049.24  4594.6 2049.03  4604.7 2047.96  4645.2 2046.11  4675.5 2045.43
  4701.3 2043.90  4715.9 2043.70  4726.1 2042.92  4771.1 2041.14  4817.0 2040.29
  4887.8 2037.78  4897.1 2037.83  4908.0 2037.00  4928.2 2037.08  4948.5 2035.79
  4997.9 2034.88  4998.2 2034.38  5001.7 2034.38  5001.9 2034.88  5010.2 2035.50
  5028.7 2040.44  5041.2 2042.65  5051.6 2043.65  5069.1 2044.31  5082.6 2045.78
  5106.2 2045.36  5127.7 2045.91  5186.3 2048.89  5201.9 2048.96  5227.0 2050.09
#Mann=5,-1,0
  4578.6    0.07       0  4701.3     0.1       0  4771.1    0.07       0
  4997.9    0.05       0  5001.9    0.07       0
Bank Sta=4997.9,5001.9
Exp/Cntr=0.3,0.1

Chan Stop Cuts=-1