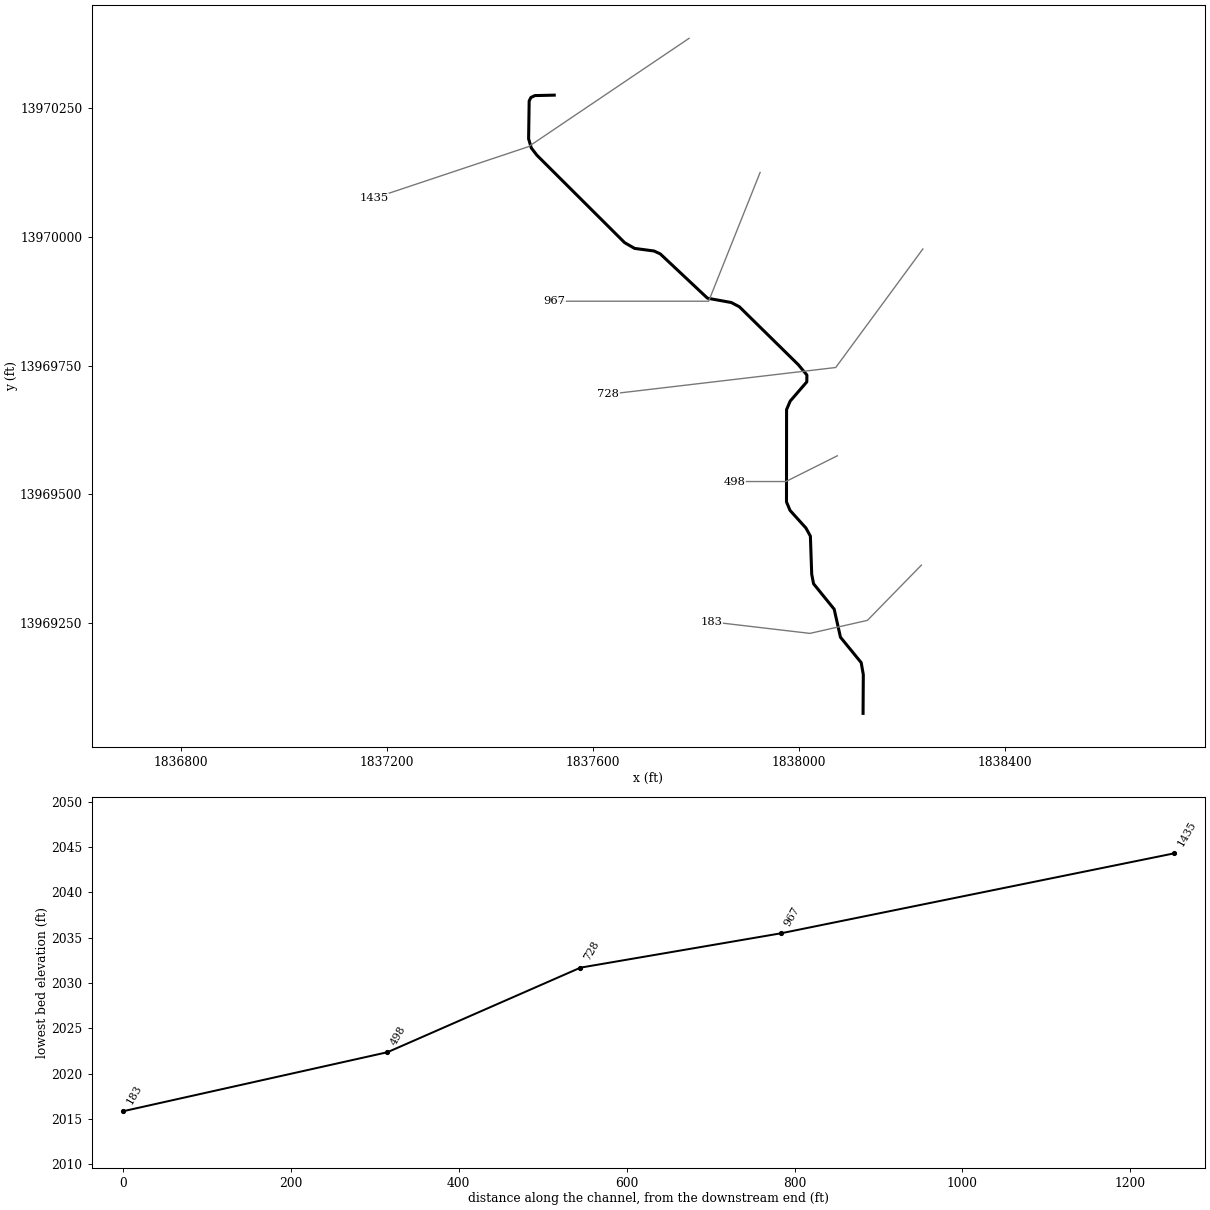
--- Stream0384.prj (project) ---

Proj Title=Stream0384 Base Level Engineering
Current Plan=p01
Default Exp/Contr=0.3,0.1
English Units
Geom File=g01
Flow File=f01
Plan File=p01
BEGIN DESCRIPTION:
Stream0384
END DESCRIPTION:

--- Stream0384.p01 (plan) ---

Plan Title=Multiple Run
Short Identifier=Multiple
Geom File=g01
Flow File=f01
Subcritical Flow
K Sum by GR= 0
Std Step Tol= 0.01
Critical Tol= 0.01
Num of Std Step Trials= 20
Max Error Tol= 0.3
Flow Tol Ratio= 0.001
Split Flow NTrial= 30
Split Flow Tol= 0.02
Split Flow Ratio= 0.02
Log Output Level= 0
Friction Slope Method= 1
Unsteady Friction Slope Method= 2
Unsteady Bridges Friction Slope Method= 1
Parabolic Critical Depth
Global Vel Dist=  1 , 1 , 1
Global Log Level= 0
CheckData=True
Encroach Param= -1, 0, 0, 0
BEGIN DESCRIPTION:
Multiple Run
END DESCRIPTION:

--- Stream0384.f01 (steady flow) ---

Flow Title=Multiple
Number of Profiles=7
Profile Names=10-year,25-year,50-year,1pct_min,100-year,1pct_plu,500-year
River Rch & RM= Stream0384,Reach-1,1435
     508     829    1123     737    1471    2935    2490
Boundary for River Rch & Prof#=Stream0384,Reach-1,1
Up Type=0
Dn Type=3
Dn Slope=0.005
Boundary for River Rch & Prof#=Stream0384,Reach-1,2
Up Type=0
Dn Type=3
Dn Slope=0.005
Boundary for River Rch & Prof#=Stream0384,Reach-1,3
Up Type=0
Dn Type=3
Dn Slope=0.005
Boundary for River Rch & Prof#=Stream0384,Reach-1,4
Up Type=0
Dn Type=3
Dn Slope=0.005
Boundary for River Rch & Prof#=Stream0384,Reach-1,5
Up Type=0
Dn Type=3
Dn Slope=0.005
Boundary for River Rch & Prof#=Stream0384,Reach-1,6
Up Type=0
Dn Type=3
Dn Slope=0.005
Boundary for River Rch & Prof#=Stream0384,Reach-1,7
Up Type=0
Dn Type=3
Dn Slope=0.005

--- Stream0384.g01 (geometry) ---

Geom Title=Existing Conditions

River Reach=Stream0384,Reach-1
Reach XY= 30
      1837525.00     13970275.00      1837487.36     13970274.13
      1837479.51     13970270.32      1837476.26     13970263.50
      1837475.18     13970190.27      1837480.37     13970172.60
      1837491.40     13970158.26      1837661.79     13969988.63
      1837681.05     13969977.53      1837718.95     13969972.46
      1837731.04     13969966.82      1837822.72     13969880.87
      1837868.95     13969872.47      1837884.68     13969864.22
      1837999.28     13969751.69      1838015.87     13969731.74
      1838015.71     13969718.47      1837983.47     13969681.19
      1837976.39     13969664.57      1837976.22     13969485.50
      1837983.14     13969468.94      1838014.11     13969434.63
      1838022.64     13969419.02      1838025.23     13969345.09
      1838028.83     13969326.58      1838068.89     13969277.18
      1838081.09     13969222.81      1838121.37     13969173.50
      1838125.48     13969150.20      1838125.00     13969075.00

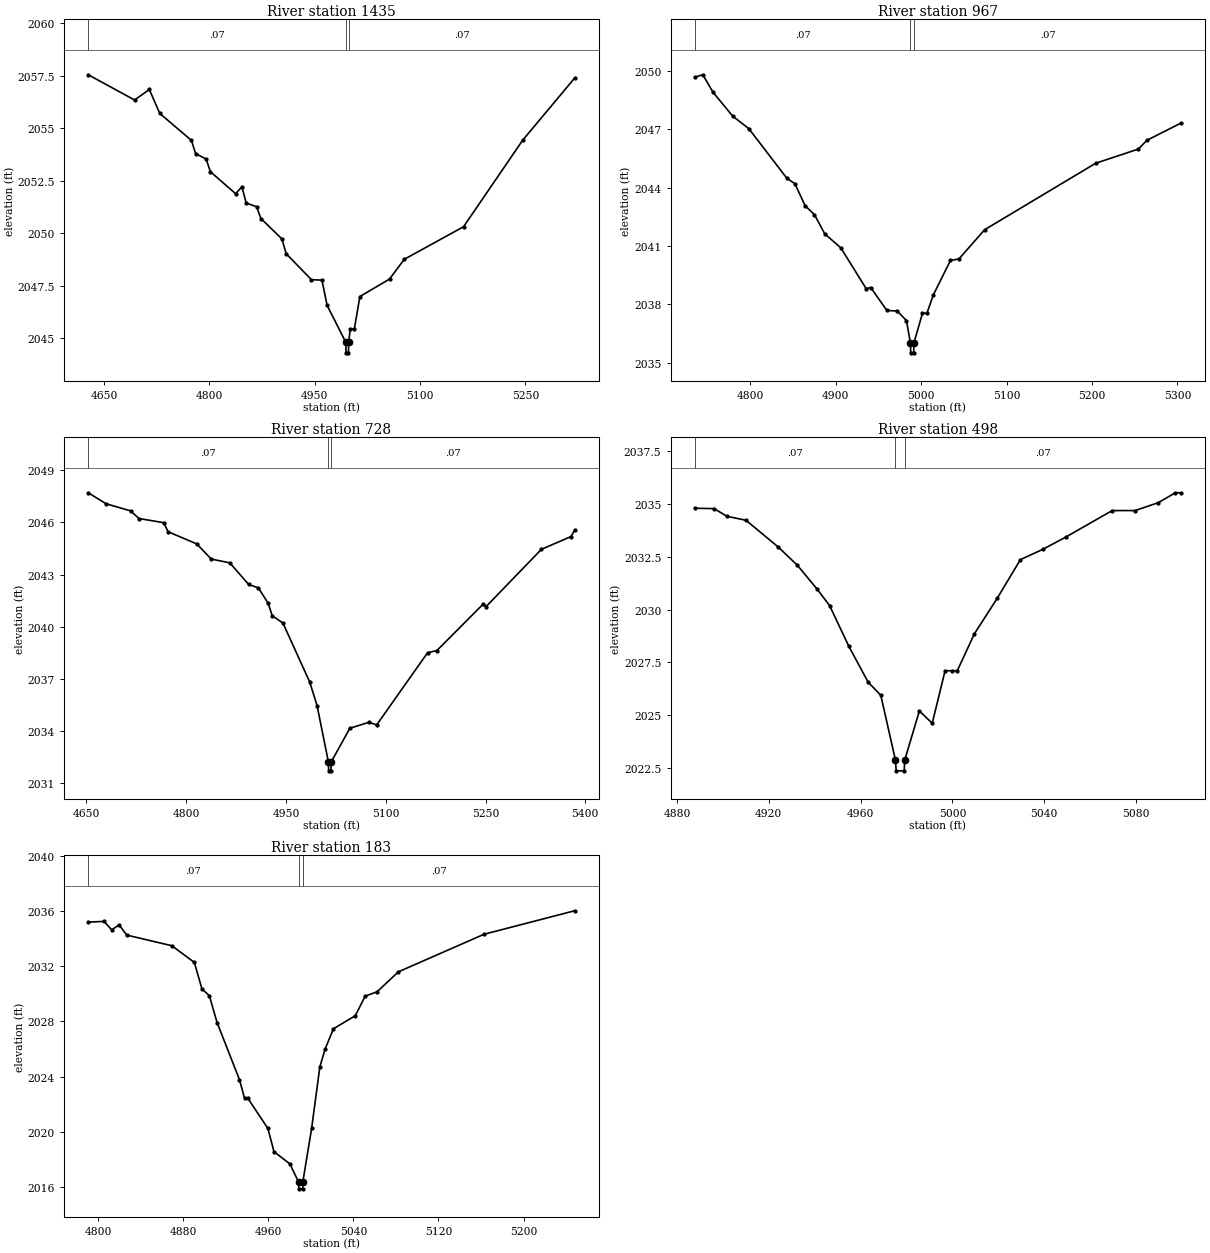
Type RM Length L Ch R = 1,1435,468,468,468
BEGIN DESCRIPTION:
Stream0384 3.0
END DESCRIPTION:
XS GIS Cut Line= 3
      1837786.91     13970385.26      1837475.00     13970175.00
      1837174.99     13970075.00
#Sta/Elev= 30
  4627.7 2057.54  4693.6 2056.34  4714.6 2056.84  4729.5 2055.70  4774.5 2054.42
  4780.5 2053.79  4795.5 2053.53  4801.5 2052.93  4837.5 2051.88  4846.4 2052.21
  4852.5 2051.44  4867.4 2051.26  4873.5 2050.70  4903.4 2049.73  4909.4 2049.03
  4945.4 2047.79  4960.4 2047.77  4967.7 2046.57  4994.4 2044.81  4994.6 2044.31
  4998.1 2044.31  4998.4 2044.81  5000.8 2045.44  5006.5 2045.44  5014.4 2046.99
  5056.6 2047.82  5077.6 2048.76  5162.0 2050.31  5246.3 2054.43  5320.1 2057.38
#Mann=3,-1,0
  4627.7    0.07       0  4994.4    0.05       0  4998.4    0.07       0
Bank Sta=4994.4,4998.4
Exp/Cntr=0.3,0.1

Type RM Length L Ch R = 1,967,239,239,239
BEGIN DESCRIPTION:
Stream0384 2.0
END DESCRIPTION:
XS GIS Cut Line= 3
      1837924.99     13970124.96      1837825.00     13969875.00
      1837525.02     13969875.00
#Sta/Elev= 30
  4735.1 2049.68  4744.5 2049.80  4756.6 2048.89  4779.5 2047.67  4798.3 2047.03
  4842.8 2044.48  4852.2 2044.20  4864.3 2043.06  4875.1 2042.61  4887.2 2041.62
  4906.0 2040.90  4935.7 2038.80  4941.0 2038.86  4959.9 2037.68  4972.0 2037.65
  4982.8 2037.16  4987.5 2036.00  4987.8 2035.50  4991.3 2035.50  4991.5 2036.00
  5001.6 2037.54  5006.8 2037.54  5014.3 2038.48  5034.3 2040.25  5044.3 2040.33
  5074.3 2041.83  5204.3 2045.25  5254.3 2045.98  5264.3 2046.43  5304.3 2047.32
#Mann=3,-1,0
  4735.1    0.07       0  4987.5    0.05       0  4991.5    0.07       0
Bank Sta=4987.5,4991.5
Exp/Cntr=0.3,0.1

Type RM Length L Ch R = 1,728,230,230,230
BEGIN DESCRIPTION:
Stream0384 1.5
END DESCRIPTION:
XS GIS Cut Line= 3
      1838241.17     13969976.39      1838071.89     13969746.34
      1837629.56     13969694.30
#Sta/Elev= 30
  4652.9 2047.70  4679.5 2047.07  4716.4 2046.66  4729.1 2046.22  4766.4 2045.98
  4772.8 2045.46  4816.0 2044.76  4837.6 2043.89  4865.7 2043.67  4893.9 2042.43
  4908.6 2042.23  4923.2 2041.35  4929.4 2040.63  4945.5 2040.21  4985.7 2036.82
  4996.8 2035.46  5013.9 2032.21  5014.2 2031.71  5017.7 2031.71  5017.9 2032.21
  5046.1 2034.16  5074.8 2034.50  5086.4 2034.35  5162.9 2038.50  5177.0 2038.63
  5246.0 2041.28  5251.0 2041.16  5334.1 2044.45  5378.4 2045.18  5383.9 2045.54
#Mann=3,-1,0
  4652.9    0.07       0  5013.9    0.05       0  5017.9    0.07       0
Bank Sta=5013.9,5017.9
Exp/Cntr=0.3,0.1

Type RM Length L Ch R = 1,498,315,315,315
BEGIN DESCRIPTION:
Stream0384 1.0
END DESCRIPTION:
XS GIS Cut Line= 3
      1838074.99     13969574.99      1837975.00     13969525.00
      1837874.99     13969525.00
#Sta/Elev= 30
  4887.8 2034.79  4896.2 2034.77  4901.8 2034.41  4910.1 2034.22  4924.1 2032.96
  4932.5 2032.09  4940.9 2030.99  4946.5 2030.19  4954.9 2028.26  4963.3 2026.57
  4968.8 2025.95  4975.2 2022.88  4975.5 2022.38  4979.0 2022.38  4979.2 2022.88
  4985.6 2025.21  4991.2 2024.63  4996.8 2027.11  4999.6 2027.11  5002.1 2027.11
  5009.6 2028.86  5019.6 2030.55  5029.6 2032.36  5039.6 2032.86  5049.6 2033.44
  5069.6 2034.68  5079.6 2034.68  5089.6 2035.05  5097.1 2035.52  5099.6 2035.52
#Mann=3,-1,0
  4887.8    0.07       0  4975.2    0.05       0  4979.2    0.07       0
Bank Sta=4975.2,4979.2
Exp/Cntr=0.3,0.1

Type RM Length L Ch R = 1,183,0,0,0
BEGIN DESCRIPTION:
Stream0384 0.0
END DESCRIPTION:
XS GIS Cut Line= 4
      1838238.28     13969362.71      1838133.50     13969255.54
      1838021.78     13969230.25      1837830.52     13969252.67
#Sta/Elev= 30
  4790.9 2035.18  4805.7 2035.23  4812.9 2034.62  4819.9 2034.98  4827.0 2034.24
  4869.4 2033.47  4890.6 2032.26  4897.7 2030.34  4904.7 2029.85  4911.9 2027.91
  4933.0 2023.77  4937.7 2022.43  4940.8 2022.43  4959.7 2020.24  4965.4 2018.56
  4980.3 2017.68  4988.5 2016.37  4988.8 2015.87  4992.3 2015.87  4992.5 2016.37
  5000.8 2020.25  5008.5 2024.70  5013.6 2026.02  5021.3 2027.46  5041.8 2028.40
  5051.1 2029.82  5062.2 2030.13  5082.3 2031.58  5162.8 2034.30  5247.9 2036.00
#Mann=3,-1,0
  4790.9    0.07       0  4988.5    0.05       0  4992.5    0.07       0
Bank Sta=4988.5,4992.5
Exp/Cntr=0.3,0.1

Chan Stop Cuts=-1