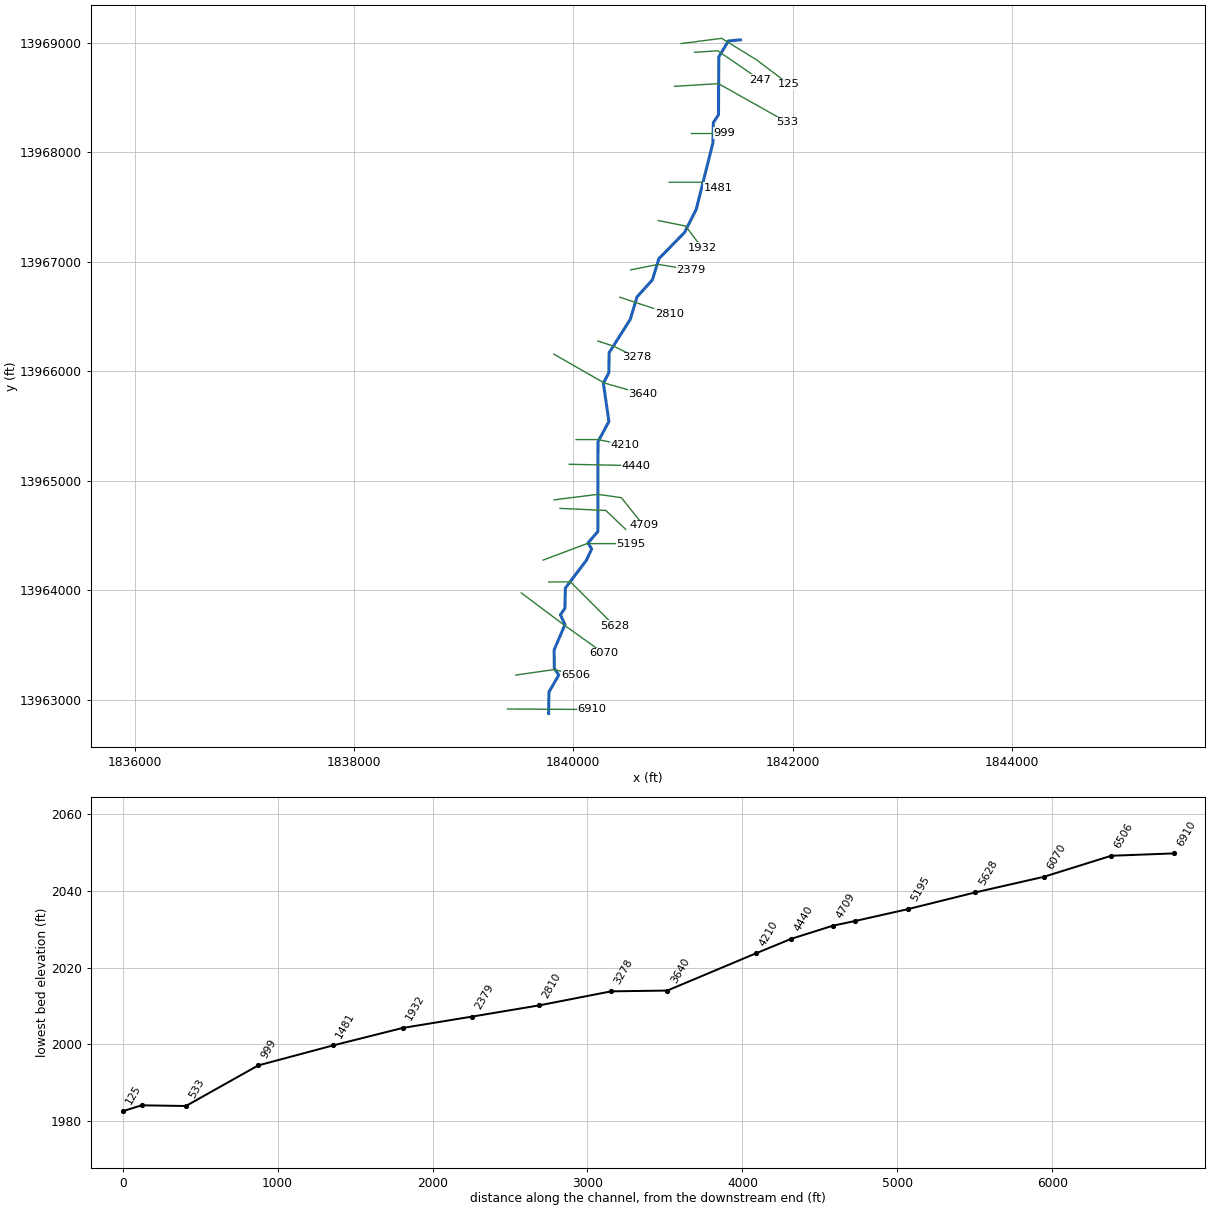
--- Stream0385.prj (project) ---

Proj Title=Stream0385 Base Level Engineering
Current Plan=p01
Default Exp/Contr=0.3,0.1
English Units
Geom File=g01
Flow File=f01
Plan File=p01
Y Axis Title=Elevation
X Axis Title(PF)=Main Channel Distance
X Axis Title(XS)=Station
BEGIN DESCRIPTION:
Stream0385
END DESCRIPTION:
DSS Export Rating Curves= 0
DSS Export Rating Curve Sorted= 0
DSS Export Volume Flow Curves= 0
DXF OffsetX= 0
DXF OffsetY= 0
DXF ScaleX= 1
DXF ScaleY= 10

--- Stream0385.p01 (plan) ---

Plan Title=Multiple Run
Short Identifier=Multiple
Geom File=g01
Flow File=f01
Subcritical Flow
K Sum by GR= 0
Std Step Tol= 0.01
Critical Tol= 0.01
Num of Std Step Trials= 20
Max Error Tol= 0.3
Flow Tol Ratio= 0.001
Split Flow NTrial= 30
Split Flow Tol= 0.02
Split Flow Ratio= 0.02
Log Output Level= 0
Friction Slope Method= 1
Unsteady Friction Slope Method= 2
Unsteady Bridges Friction Slope Method= 1
Parabolic Critical Depth
Global Vel Dist=  1 , 1 , 1
Global Log Level= 0
CheckData=True
Encroach Param= -1, 0, 0, 0
BEGIN DESCRIPTION:
Multiple Run
END DESCRIPTION:

--- Stream0385.f01 (steady flow) ---

Flow Title=Multiple
Program Version=4.10
Number of Profiles= 7
Profile Names=10-year,25-year,50-year,1pct_min,100-year,1pct_plu,500-year
River Rch & RM=Stream0385,Reach-1         ,6910
    1440    2497    3517    2391    4770    9518    8680
River Rch & RM=Stream0385,Reach-1         ,3640
    2235    3960    5657    3893    7768   15498   14495
Boundary for River Rch & Prof#=Stream0385,Reach-1         , 1
Up Type= 0
Dn Type= 3
Dn Slope=0.01
Boundary for River Rch & Prof#=Stream0385,Reach-1         , 2
Up Type= 0
Dn Type= 3
Dn Slope=0.01
Boundary for River Rch & Prof#=Stream0385,Reach-1         , 3
Up Type= 0
Dn Type= 3
Dn Slope=0.01
Boundary for River Rch & Prof#=Stream0385,Reach-1         , 4
Up Type= 0
Dn Type= 3
Dn Slope=0.01
Boundary for River Rch & Prof#=Stream0385,Reach-1         , 5
Up Type= 0
Dn Type= 3
Dn Slope=0.01
Boundary for River Rch & Prof#=Stream0385,Reach-1         , 6
Up Type= 0
Dn Type= 3
Dn Slope=0.01
Boundary for River Rch & Prof#=Stream0385,Reach-1         , 7
Up Type= 0
Dn Type= 3
Dn Slope=0.01
DSS Import GetInterval= 0
DSS Import GetPeak= 0
DSS Import FillOption= 0

--- Stream0385.g01 (geometry) ---

Geom Title=Existing Conditions
Program Version=4.10

River Reach=Stream0385      ,Reach-1
Reach XY= 30
        1839775.       13962875.      1839777.23     13963069.08
      1839867.47     13963224.99      1839826.38     13963285.44
      1839825.07     13963454.97      1839924.19     13963685.71
      1839882.59     13963774.99      1839923.62     13963835.44
      1839927.24     13964019.07      1840119.19     13964272.71
      1840167.23     13964375.09      1840134.32     13964431.66
      1840223.94     13964535.43      1840225.06     13965354.97
      1840324.49     13965540.21      1840274.29     13965890.29
       1840323.8      13965985.5      1840327.24     13966169.07
      1840519.46     13966472.58      1840580.84     13966677.29
      1840721.51     13966833.48      1840780.83      13967027.3
      1841014.24     13967265.32      1841121.17     13967476.58
      1841273.78     13968085.51      1841277.26     13968269.06
      1841324.48     13968340.22      1841327.24     13968869.07
      1841414.82     13969014.72        1841525.       13969025.

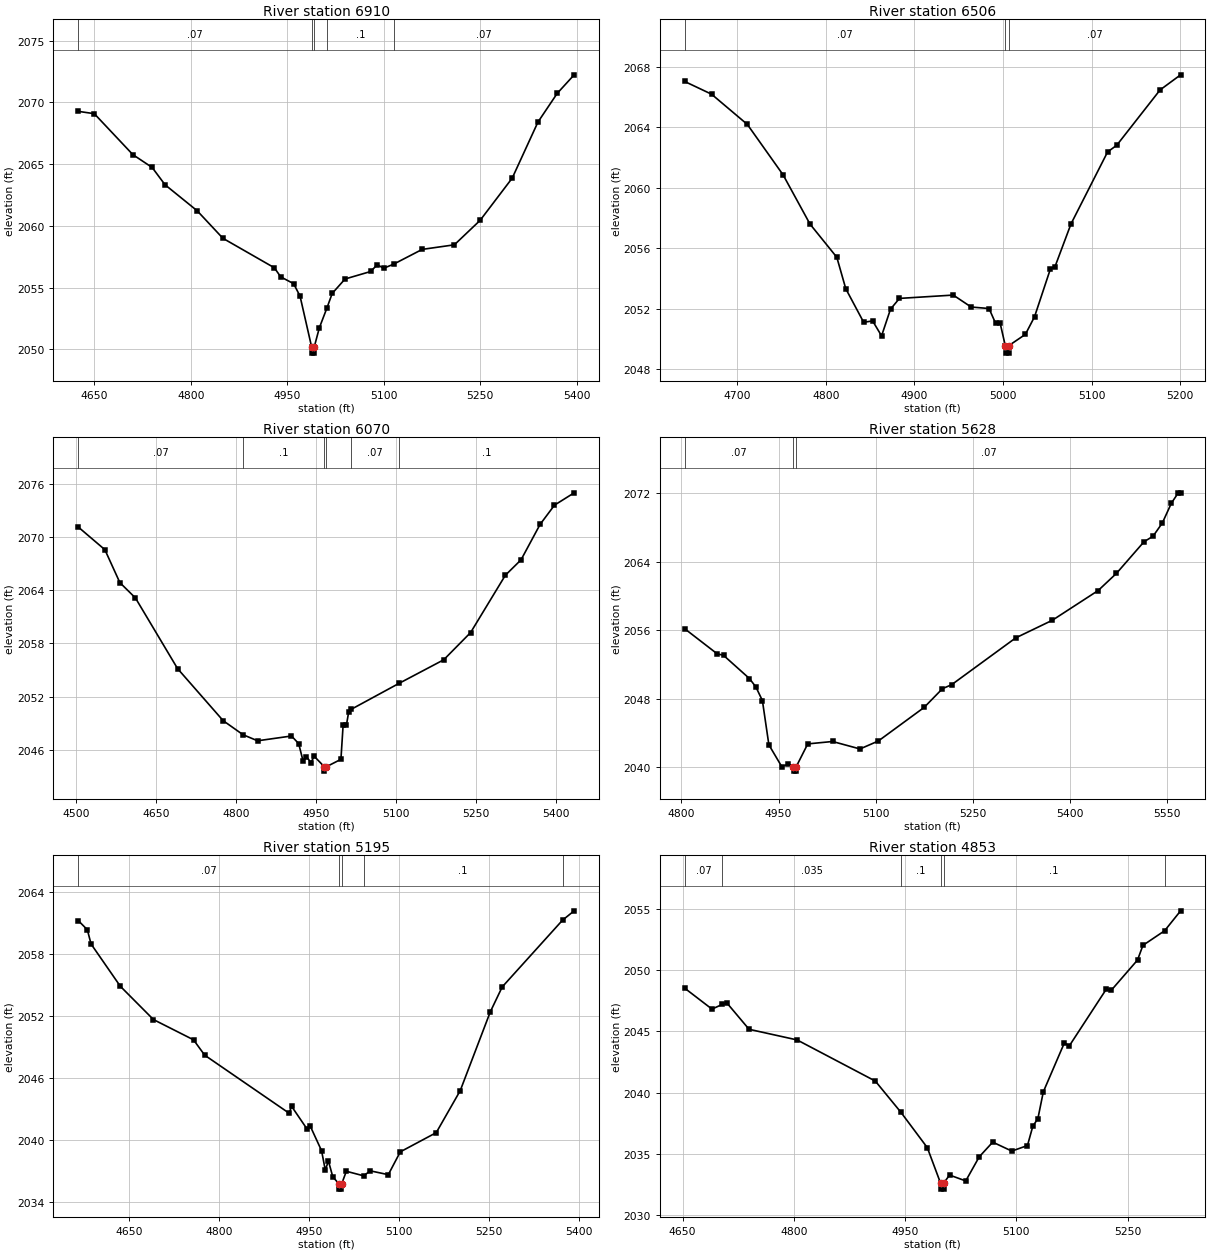
Type RM Length L Ch R = 1 ,6910    ,404,404,404
BEGIN DESCRIPTION:
Stream0385 15.0
END DESCRIPTION:
XS GIS Cut Line= 2
      1839399.98     13962914.74      1840171.26     13962910.41
#Sta/Elev= 30
    4625 2069.28    4650 2069.09    4710 2065.77    4740 2064.73    4760 2063.33
    4810 2061.22    4850 2058.99    4930  2056.6    4940 2055.86    4960 2055.31
    4970  2054.3    4988 2050.18  4988.2 2049.68  4991.8 2049.68  4992.1 2050.18
    5000 2051.73  5011.9 2053.35    5020 2054.52    5040 2055.69    5080  2056.3
    5090 2056.85    5100 2056.56  5115.5 2056.89    5160 2058.09    5210 2058.46
    5250 2060.44    5300 2063.87    5340 2068.41    5370 2070.74  5396.3 2072.24
#Mann= 5 ,-1 , 0
    4625     .07       0    4988     .05       0  4992.1     .07       0
  5011.9      .1       0  5115.5     .07       0
Bank Sta=4988,4992.1
XS Rating Curve= 0 ,0
Exp/Cntr=0.3,0.1

Type RM Length L Ch R = 1 ,6506    ,436,436,436
BEGIN DESCRIPTION:
Stream0385 14.0
END DESCRIPTION:
XS GIS Cut Line= 3
      1839474.99       13963225.        1839825.       13963275.
      1840024.98     13963225.01
#Sta/Elev= 30
  4640.8 2067.04  4671.1  2066.2  4711.5  2064.2  4751.9 2060.86  4782.2 2057.61
  4812.5 2055.41  4822.6 2053.33  4842.8 2051.11  4852.9  2051.2    4863 2050.21
  4873.1 2051.98  4883.2 2052.69  4943.9 2052.91  4964.1 2052.12  4984.3 2052.02
  4991.8 2051.03  4996.9 2051.03  5002.6 2049.57  5002.9 2049.07  5006.5 2049.07
  5006.7 2049.57  5025.3 2050.31  5035.6 2051.47  5053.6 2054.65  5058.8  2054.8
  5076.8 2057.62  5118.1 2062.38  5128.4 2062.82  5177.3 2066.48  5200.5 2067.48
#Mann= 3 ,-1 , 0
  4640.8     .07       0  5002.6     .05       0  5006.7     .07       0
Bank Sta=5002.6,5006.7
XS Rating Curve= 0 ,0
Exp/Cntr=0.3,0.1

Type RM Length L Ch R = 1 ,6070    ,442,442,442
BEGIN DESCRIPTION:
Stream0385 13.0
END DESCRIPTION:
XS GIS Cut Line= 3
      1839525.02     13963974.98        1839925.       13963675.
      1840275.01     13963424.99
#Sta/Elev= 30
    4504 2071.11    4554 2068.55  4582.1 2064.84  4611.3 2063.11  4690.4 2055.14
  4775.8 2049.28  4813.2 2047.69  4840.4 2047.01    4904 2047.55  4917.5 2046.69
  4925.8  2044.7  4932.1 2045.22  4940.4 2044.56  4946.7 2045.26  4965.4 2044.09
  4965.7 2043.59  4969.6 2044.09  4996.7 2044.92  5000.8 2048.77    5007 2048.77
  5011.3 2050.28  5016.4 2050.57  5105.3 2053.47  5189.5 2056.14  5239.9 2059.21
  5305.1 2065.67  5334.5 2067.41  5370.2  2071.4  5397.2 2073.57  5434.1 2074.96
#Mann= 6 ,-1 , 0
    4504     .07       0  4813.2      .1       0  4965.4     .05       0
  4969.6      .1       0  5016.4     .07       0  5105.3      .1       0
Bank Sta=4965.4,4969.6
XS Rating Curve= 0 ,0
Exp/Cntr=0.3,0.1

Type RM Length L Ch R = 1 ,5628    ,433,433,433
BEGIN DESCRIPTION:
Stream0385 12.0
END DESCRIPTION:
XS GIS Cut Line= 3
      1839775.02       13964075.        1839975.       13964075.
      1840375.03     13963674.97
#Sta/Elev= 30
  4805.1 2056.17  4855.1 2053.25  4865.1 2053.06  4905.1 2050.35  4915.1 2049.36
  4925.1 2047.78  4935.1 2042.61  4955.1 2040.05  4965.1 2040.37  4972.9 2040.04
  4973.2 2039.54  4976.9 2039.54  4977.2 2040.04  4995.1 2042.72  5033.4    2043
  5075.8 2042.13  5104.1 2043.06  5174.8 2046.98  5203.1 2049.17  5217.2 2049.63
  5316.2  2055.1  5372.8 2057.16  5443.5 2060.63  5471.8 2062.64  5514.2 2066.32
  5528.3 2066.98  5542.5 2068.51  5556.6 2070.84  5567.2 2072.04  5570.8 2072.04
#Mann= 3 ,-1 , 0
  4805.1     .07       0  4972.9     .05       0  4977.2     .07       0
Bank Sta=4972.9,4977.2
XS Rating Curve= 0 ,0
Exp/Cntr=0.3,0.1

Type RM Length L Ch R = 1 ,5195    ,342,342,342
BEGIN DESCRIPTION:
Stream0385 11.0
END DESCRIPTION:
XS GIS Cut Line= 3
      1839724.97     13964274.99        1840125.       13964425.
      1840524.96       13964425.
#Sta/Elev= 30
  4565.2 2061.22  4580.4 2060.33  4586.6 2058.95  4635.5 2054.85  4690.7 2051.63
  4757.5 2049.67  4776.2 2048.18  4916.8 2042.57  4921.2 2043.22    4947 2041.02
  4952.4 2041.29  4971.1 2038.93  4977.3 2037.06  4982.6 2037.93  4989.8  2036.4
  5000.3 2035.71  5000.5 2035.21  5004.3 2035.21  5004.6 2035.71  5012.4 2036.94
  5041.2  2036.5  5052.4 2036.98  5082.4 2036.61  5102.4 2038.82  5162.4 2040.68
  5202.4 2044.75  5252.4 2052.36  5272.4 2054.79  5373.1 2061.26  5392.4 2062.16
#Mann= 5 ,-1 , 0
  4565.2     .07       0  5000.3     .05       0  5004.6     .07       0
  5041.2      .1       0  5373.1     .07       0
Bank Sta=5000.3,5004.6
XS Rating Curve= 0 ,0
Exp/Cntr=0.3,0.1

Type RM Length L Ch R = 1 ,4853    ,144,144,144
BEGIN DESCRIPTION:
Mapping XS ec27aa1a
END DESCRIPTION:
XS GIS Cut Line= 3
      1839878.27     13964746.75       1840296.3     13964728.09
      1840477.51     13964555.64
#Sta/Elev= 30
  4652.9 2048.53  4689.7 2046.82  4703.8 2047.21  4709.7 2047.33  4739.7 2045.17
  4804.5  2044.3  4909.9 2040.94  4944.4 2038.39    4980  2035.5  4997.8 2032.61
  4998.1 2032.11  5001.9 2032.11  5002.2 2032.61    5010 2033.26  5031.8 2032.78
    5050 2034.75  5068.2 2035.95  5093.9 2035.22    5115 2035.67  5122.2 2037.24
  5129.1 2037.88  5136.4 2040.06  5164.7 2044.05  5171.6 2043.83  5221.3 2048.45
  5228.2 2048.37  5263.4 2050.83  5270.7 2052.03  5299.9 2053.22  5321.5 2054.85
#Mann= 6 ,-1 , 0
  4652.9     .07       0  4703.8    .035       0  4944.4      .1       0
  4997.8     .05       0  5002.2      .1       0  5299.9     .07       0
Bank Sta=4997.8,5002.2
XS Rating Curve= 0 ,0
Exp/Cntr=0.3,0.1

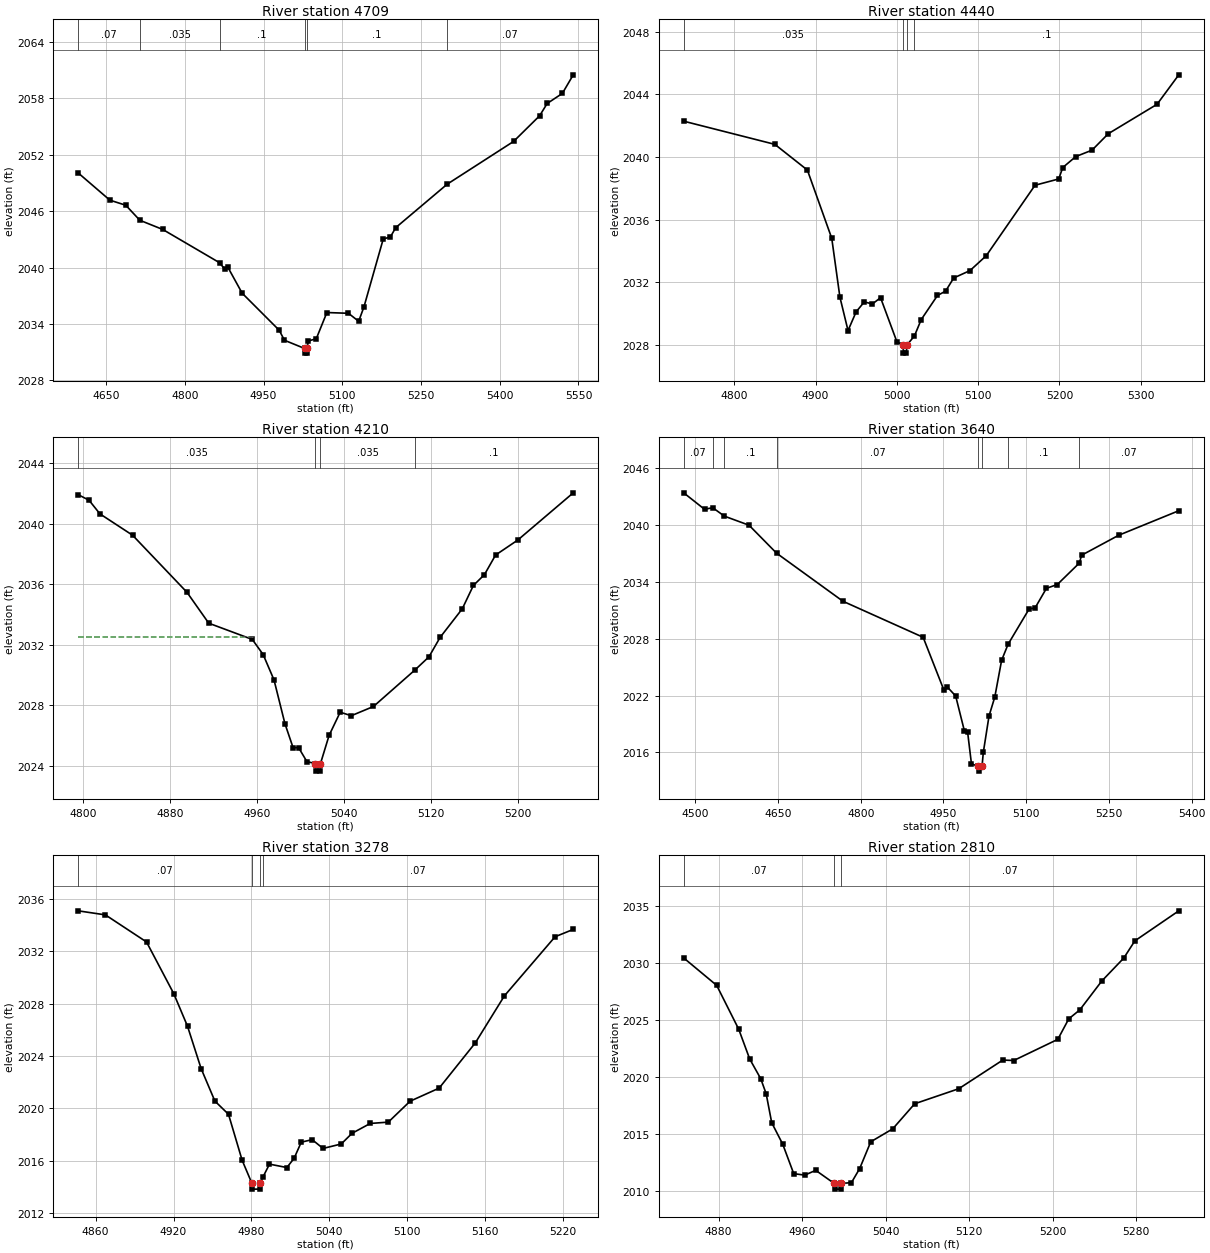
Type RM Length L Ch R = 1 ,4709    ,269,269,269
BEGIN DESCRIPTION:
Stream0385 10.0
END DESCRIPTION:
XS GIS Cut Line= 4
      1839825.02       13964825.        1840225.       13964875.
      1840437.89     13964845.01      1840640.83       13964591.
#Sta/Elev= 30
  4596.9 2050.07  4657.3 2047.17  4687.6 2046.63  4714.4 2045.03  4758.1 2044.05
  4866.3 2040.51  4876.5  2039.8  4881.6 2040.08  4909.3 2037.27  4979.8 2033.33
  4989.9 2032.26  5028.1 2031.39  5028.4 2030.89  5032.2 2030.89  5032.5 2031.39
  5035.6 2032.19  5050.5 2032.42  5070.7 2035.21  5111.8 2035.13  5131.3 2034.28
  5141.4 2035.82    5178 2043.02  5191.9 2043.28    5202 2044.25  5299.9 2048.87
  5426.4 2053.42    5476 2056.15  5490.4 2057.46  5519.3 2058.53  5540.1 2060.51
#Mann= 6 ,-1 , 0
  4596.9     .07       0  4714.4    .035       0  4866.3      .1       0
  5028.1     .05       0  5032.5      .1       0  5299.9     .07       0
Bank Sta=5028.1,5032.5
XS Rating Curve= 0 ,0
Exp/Cntr=0.3,0.1

Type RM Length L Ch R = 1 ,4440    ,230,230,230
BEGIN DESCRIPTION:
Mapping XS 50a654ac
END DESCRIPTION:
XS GIS Cut Line= 2
      1839962.95     13965149.49      1840571.72     13965137.07
#Sta/Elev= 30
  4737.9 2042.28    4850  2040.8    4890 2039.16    4920  2034.8    4930 2031.05
    4940 2028.91    4950 2030.11    4960 2030.74    4970 2030.61    4980 2031.01
    5000 2028.21  5007.8 2027.97  5008.1 2027.47  5011.9 2027.47  5012.2 2027.97
  5021.7 2028.57    5030 2029.61    5050 2031.15    5060 2031.43    5070 2032.27
    5090 2032.74    5110 2033.69    5170 2038.19  5199.1 2038.59  5204.1 2039.32
  5220.1 2040.02  5240.1 2040.43  5260.1 2041.48  5320.1 2043.36  5346.8 2045.24
#Mann= 4 ,-1 , 0
  4737.9    .035       0  5007.8    .035       0  5012.2    .035       0
  5021.7      .1       0
Bank Sta=5007.8,5012.2
XS Rating Curve= 0 ,0
Exp/Cntr=0.3,0.1

Type RM Length L Ch R = 1 ,4210    ,570,570,570
BEGIN DESCRIPTION:
Stream0385 9.0
END DESCRIPTION:
XS GIS Cut Line= 3
        1840025.       13965375.        1840225.       13965375.
      1840475.05     13965324.99
#Sta/Elev= 30
  4795.8 2041.92  4805.8 2041.55  4815.8 2040.65  4845.8 2039.24  4895.8 2035.47
  4915.8 2033.43  4955.8 2032.36  4965.8 2031.36  4975.8 2029.68  4985.8  2026.8
  4993.3 2025.21  4998.4 2025.21    5006 2024.29  5013.9 2024.16  5014.2 2023.66
  5018.2 2023.66  5018.5 2024.16  5026.4 2026.02  5036.6 2027.55  5046.8 2027.32
  5067.2 2027.93  5105.3 2030.34  5118.2 2031.21  5128.4 2032.49  5148.8 2034.38
    5159 2035.92  5169.2 2036.64  5179.4 2037.93  5199.8 2038.92  5250.8 2042.04
#Mann= 4 ,-1 , 0
  4795.8    .035       0  5013.9    .035       0  5018.5    .035       0
  5105.3      .1       0
#XS Ineff= 2 , 0
         4956.26 2032.54
Permanent Ineff=
       F       F
Bank Sta=5013.9,5018.5
XS Rating Curve= 0 ,0
Exp/Cntr=0.3,0.1

Type RM Length L Ch R = 1 ,3640    ,362,362,362
BEGIN DESCRIPTION:
Stream0385 8.0
END DESCRIPTION:
XS GIS Cut Line= 3
       1839822.2      13966155.2      1840281.32     13965892.27
      1840635.59     13965790.05
#Sta/Elev= 30
  4478.9  2043.4  4516.7 2041.66  4531.5 2041.83  4552.6 2040.94  4597.4 2039.98
  4647.3 2037.03  4767.8 2031.95  4913.1 2028.15  4950.5 2022.61  4956.3 2022.94
  4972.1 2021.95  4987.9 2018.27  4993.7 2018.16  5000.7 2014.79  5013.3 2014.52
  5013.8 2014.02  5019.9 2014.52  5022.2 2015.99  5032.6 2019.85    5043 2021.83
  5055.4 2025.72  5067.2 2027.42  5105.5 2031.16  5115.9 2031.23  5136.7 2033.32
  5156.4 2033.72  5196.4 2035.99  5200.4 2036.81  5267.7 2038.92  5376.7 2041.51
#Mann= 8 ,-1 , 0
  4478.9     .07       0  4531.5    .035       0  4552.6      .1       0
  4647.3     .07       0  5013.3     .05       0  5019.9     .07       0
  5067.2      .1       0  5196.4     .07       0
Bank Sta=5013.3,5019.9
XS Rating Curve= 0 ,0
Exp/Cntr=0.3,0.1

Type RM Length L Ch R = 1 ,3278    ,468,468,468
BEGIN DESCRIPTION:
Stream0385 7.0
END DESCRIPTION:
XS GIS Cut Line= 3
      1840225.04     13966274.99        1840375.       13966225.
      1840575.02     13966124.99
#Sta/Elev= 30
  4846.5 2035.09  4867.5 2034.78  4899.2 2032.71  4920.2 2028.76  4930.8 2026.27
  4941.3 2023.03  4951.9 2020.55  4962.4 2019.54  4972.9 2016.03  4980.2 2014.32
  4980.7 2013.82  4986.3 2013.82  4986.8 2014.32    4989 2014.75    4994 2015.73
  5007.4 2015.47    5013 2016.18  5018.5 2017.41  5026.9  2017.6  5035.3 2016.93
  5049.3 2017.27  5057.7 2018.09  5071.7 2018.84  5085.6 2018.94  5102.4 2020.54
  5124.8 2021.54  5152.7    2025  5175.1 2028.59  5214.2 2033.11  5228.2 2033.67
#Mann= 4 ,-1 , 0
  4846.5     .07       0  4980.2     .05       0  4986.8     .07       0
    4989     .07       0
Bank Sta=4980.2,4986.8
XS Rating Curve= 0 ,0
Exp/Cntr=0.3,0.1

Type RM Length L Ch R = 1 ,2810    ,431,431,431
BEGIN DESCRIPTION:
Stream0385 6.0
END DESCRIPTION:
XS GIS Cut Line= 3
      1840425.02     13966674.99        1840575.       13966625.
      1840874.98     13966525.01
#Sta/Elev= 30
  4846.5 2030.46  4878.1 2028.05  4899.2  2024.2  4909.7 2021.59  4920.3 2019.85
  4925.5 2018.53  4930.8 2015.99  4941.4 2014.09  4951.9 2011.51  4962.4 2011.38
    4973  2011.8  4990.7 2010.65  4991.2 2010.15  4996.9 2010.15  4997.4 2010.65
  5007.2 2010.72  5015.1 2011.96  5025.7 2014.31  5046.8 2015.45  5067.8 2017.65
    5110 2018.97  5152.2 2021.49  5162.7 2021.45  5204.9 2023.31  5215.4 2025.11
    5226  2025.9    5247 2028.43  5268.1 2030.45  5278.7 2031.96  5320.8  2034.6
#Mann= 3 ,-1 , 0
  4846.5     .07       0  4990.7     .05       0  4997.4     .07       0
Bank Sta=4990.7,4997.4
XS Rating Curve= 0 ,0
Exp/Cntr=0.3,0.1

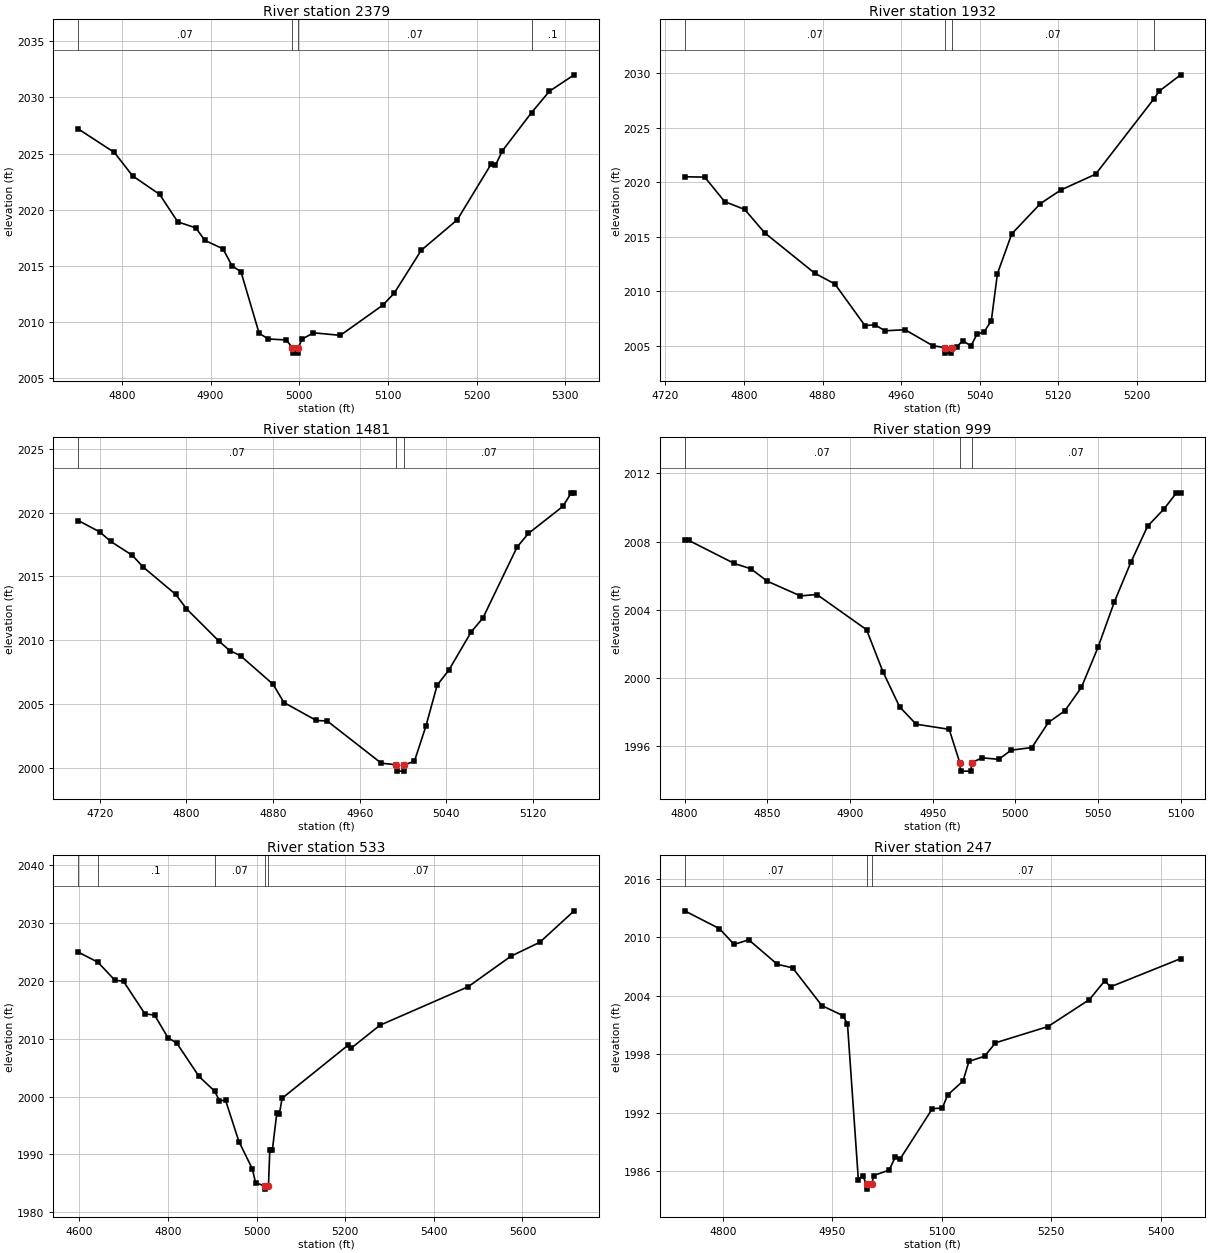
Type RM Length L Ch R = 1 ,2379    ,447,447,447
BEGIN DESCRIPTION:
Stream0385 5.0
END DESCRIPTION:
XS GIS Cut Line= 3
      1840525.02       13966925.        1840775.       13966975.
      1841075.03       13966925.
#Sta/Elev= 30
  4750.8  2027.2  4791.6  2025.1    4812 2023.03  4842.6 2021.37    4863 2018.93
  4883.4 2018.39  4893.6 2017.28    4914 2016.53  4924.2 2015.02  4934.3 2014.49
  4954.7 2009.03  4964.9 2008.51  4985.3 2008.42  4992.1 2007.75  4992.6 2007.25
  4998.4 2007.25  4998.9 2007.75  5003.2 2008.49  5015.9 2009.06  5046.3 2008.83
  5094.4 2011.53  5107.1 2012.59  5137.5  2016.4  5178.1 2019.11  5216.1 2024.04
  5221.2 2023.96  5228.8 2025.23  5261.9 2028.65    5282 2030.55  5309.9 2032.01
#Mann= 4 ,-1 , 0
  4750.8     .07       0  4992.1     .05       0  4998.9     .07       0
  5261.9      .1       0
Bank Sta=4992.1,4998.9
XS Rating Curve= 0 ,0
Exp/Cntr=0.3,0.1

Type RM Length L Ch R = 1 ,1932    ,451,451,451
BEGIN DESCRIPTION:
Stream0385 4.0
END DESCRIPTION:
XS GIS Cut Line= 3
      1840775.04     13967374.99        1841025.       13967325.
        1841175.       13967125.
#Sta/Elev= 30
  4739.6 2020.49    4760 2020.46  4780.3 2018.21  4800.7 2017.49  4821.1 2015.34
  4872.1 2011.63  4892.5 2010.65  4923.1 2006.83  4933.3  2006.9  4943.5 2006.35
  4963.9 2006.45    4992 2004.99  5004.5  2004.8    5005  2004.3    5011  2004.3
  5011.5  2004.8  5016.4 2004.84  5022.6 2005.45    5031 2004.96  5037.2 2006.03
  5044.5 2006.25  5051.8 2007.29    5058  2011.6  5072.6 2015.25  5101.8 2018.03
  5122.6 2019.28    5158 2020.73  5217.5 2027.67  5222.6 2028.34  5244.5 2029.85
#Mann= 4 ,-1 , 0
  4739.6     .07       0  5004.5     .05       0  5011.5     .07       0
  5217.5      .1       0
Bank Sta=5004.5,5011.5
XS Rating Curve= 0 ,0
Exp/Cntr=0.3,0.1

Type RM Length L Ch R = 1 ,1481    ,482,482,482
BEGIN DESCRIPTION:
Stream0385 3.0
END DESCRIPTION:
XS GIS Cut Line= 3
        1840875.       13967725.        1841175.       13967725.
      1841324.99       13967675.
#Sta/Elev= 30
    4700 2019.39    4720 2018.49    4730 2017.75    4750 2016.66    4760 2015.74
    4790  2013.6    4800 2012.47    4830 2009.93    4840 2009.19    4850 2008.78
    4880 2006.55    4890 2005.12    4920 2003.71    4930 2003.67    4980 2000.36
  4993.9 2000.24  4994.4 1999.74  5000.5 1999.74    5001 2000.24  5010.5  2000.5
  5021.1 2003.25  5031.6 2006.49  5042.2 2007.64  5063.2 2010.68  5073.8 2011.74
  5105.4 2017.31  5115.9 2018.38  5147.6 2020.49  5155.5 2021.56  5158.1 2021.56
#Mann= 3 ,-1 , 0
    4700     .07       0  4993.9     .05       0    5001     .07       0
Bank Sta=4993.9,5001
XS Rating Curve= 0 ,0
Exp/Cntr=0.3,0.1

Type RM Length L Ch R = 1 ,999     ,466,466,466
BEGIN DESCRIPTION:
Stream0385 2.0
END DESCRIPTION:
XS GIS Cut Line= 3
        1841075.       13968175.        1841275.       13968175.
        1841375.       13968175.
#Sta/Elev= 30
    4800 2008.07  4802.5 2008.07    4830 2006.72    4840 2006.41    4850 2005.68
    4870 2004.82    4880  2004.9    4910 2002.84    4920 2000.36    4930 1998.32
    4940  1997.3    4960    1997  4966.4 1995.05  4966.9 1994.55  4973.1 1994.55
  4973.6 1995.05    4980 1995.33    4990 1995.24  4997.5 1995.78    5010 1995.93
    5020  1997.4    5030 1998.09    5040 1999.46    5050  2001.8    5060 2004.49
    5070 2006.81    5080  2008.9    5090 2009.92  5097.5 2010.86    5100 2010.86
#Mann= 3 ,-1 , 0
    4800     .07       0  4966.4     .05       0  4973.6     .07       0
Bank Sta=4966.4,4973.6
XS Rating Curve= 0 ,0
Exp/Cntr=0.3,0.1

Type RM Length L Ch R = 1 ,533     ,286,286,286
BEGIN DESCRIPTION:
Stream0385 1.0
END DESCRIPTION:
XS GIS Cut Line= 3
      1840922.83     13968600.78        1841325.       13968625.
      1841949.38     13968273.14
#Sta/Elev= 30
  4597.1 2024.99  4641.5 2023.25  4679.4 2020.17  4699.5 2019.92  4747.5 2014.33
  4769.6 2014.09  4799.6  2010.2  4819.7 2009.24  4869.8  2003.5    4905 2000.95
  4915.8 1999.33  4929.9 1999.34  4959.9 1992.23    4990 1987.54  4997.5 1985.13
  5019.3 1984.51  5019.8 1984.01  5026.6 1984.51  5029.6 1990.78  5035.4 1990.77
  5045.5  1997.2  5051.3 1997.05  5057.4 1999.72  5206.6 2008.92  5213.1 2008.37
  5278.1 2012.34  5477.5 2019.01  5573.9 2024.28  5639.3  2026.7  5716.7 2032.13
#Mann= 5 ,-1 , 0
  4597.1     .07       0  4641.5      .1       0    4905     .07       0
  5019.3     .05       0  5026.6     .07       0
Bank Sta=5019.3,5026.6
XS Rating Curve= 0 ,0
Exp/Cntr=0.3,0.1

Type RM Length L Ch R = 1 ,247     ,122,122,122
BEGIN DESCRIPTION:
Stream0385 0.0
END DESCRIPTION:
XS GIS Cut Line= 3
      1841107.43     13968911.25       1841318.1     13968925.34
      1841703.98     13968659.73
#Sta/Elev= 30
  4747.9  2012.7  4795.6 2010.87  4815.6 2009.26  4835.7 2009.73  4874.9 2007.22
  4895.8 2006.86  4935.9 2002.99  4964.9 2001.96    4971  2001.1  4985.9 1985.13
  4991.9 1985.55  4997.1 1984.69  4997.6 1984.19  5004.4 1984.69  5006.8 1985.58
  5028.1 1986.14  5036.6  1987.5  5042.7 1987.23  5087.3 1992.43    5101  1992.5
  5108.3 1993.84  5129.3 1995.26  5137.4 1997.27    5159 1997.81  5173.8 1999.18
  5245.6 2000.84  5302.4  2003.6  5323.4 2005.52  5331.6 2004.92  5427.5  2007.8
#Mann= 3 ,-1 , 0
  4747.9     .07       0  4997.1     .05       0  5004.4     .07       0
Bank Sta=4997.1,5004.4
XS Rating Curve= 0 ,0
Exp/Cntr=0.3,0.1

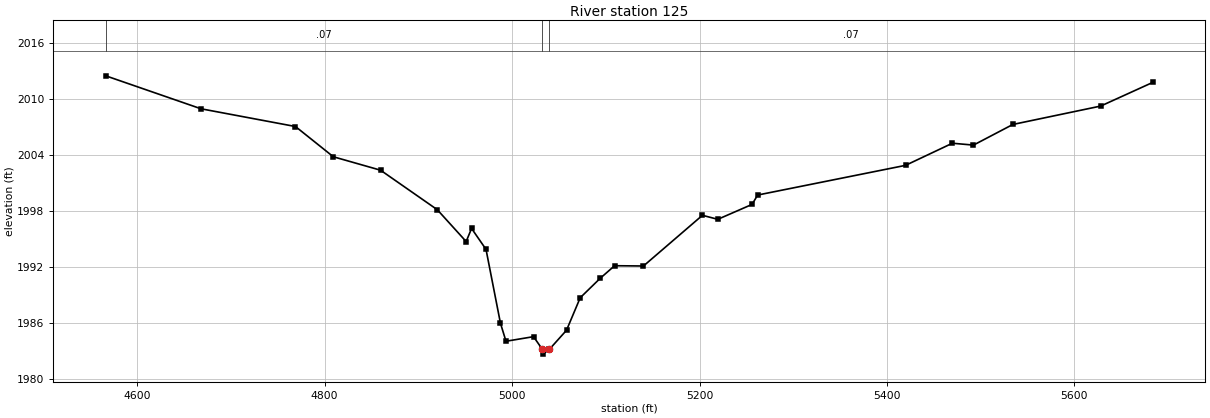
Type RM Length L Ch R = 1 ,125     ,0,0,0
BEGIN DESCRIPTION:
Stream0385 0.1
END DESCRIPTION:
XS GIS Cut Line= 4
      1840984.24     13968991.13      1841353.14     13969038.87
      1841669.98     13968843.56      1841968.04     13968618.94
#Sta/Elev= 30
  4566.5 2012.46  4668.1 2008.93  4768.9 2007.03  4809.3 2003.79  4859.7 2002.35
  4920.2 1998.12    4951 1994.71  4956.8 1996.11  4972.2 1993.87  4987.6 1985.96
  4993.5 1984.03  5022.9 1984.52  5032.4 1983.15  5032.9 1982.65  5039.7 1983.15
  5058.1 1985.21  5072.7 1988.69    5094 1990.77  5109.4 1992.12  5140.2 1992.09
  5203.1 1997.52  5219.5 1997.09  5256.1 1998.69    5262 1999.69  5419.8 2002.87
  5469.8 2005.24  5492.3 2005.04  5534.3 2007.25    5628 2009.22  5683.9 2011.77
#Mann= 3 ,-1 , 0
  4566.5     .07       0  5032.4     .05       0  5039.7     .07       0
Bank Sta=5032.4,5039.7
XS Rating Curve= 0 ,0
Exp/Cntr=0.3,0.1

Chan Stop Cuts=-1
Use User Specified Reach Order=0
Composite Channel Slope=5