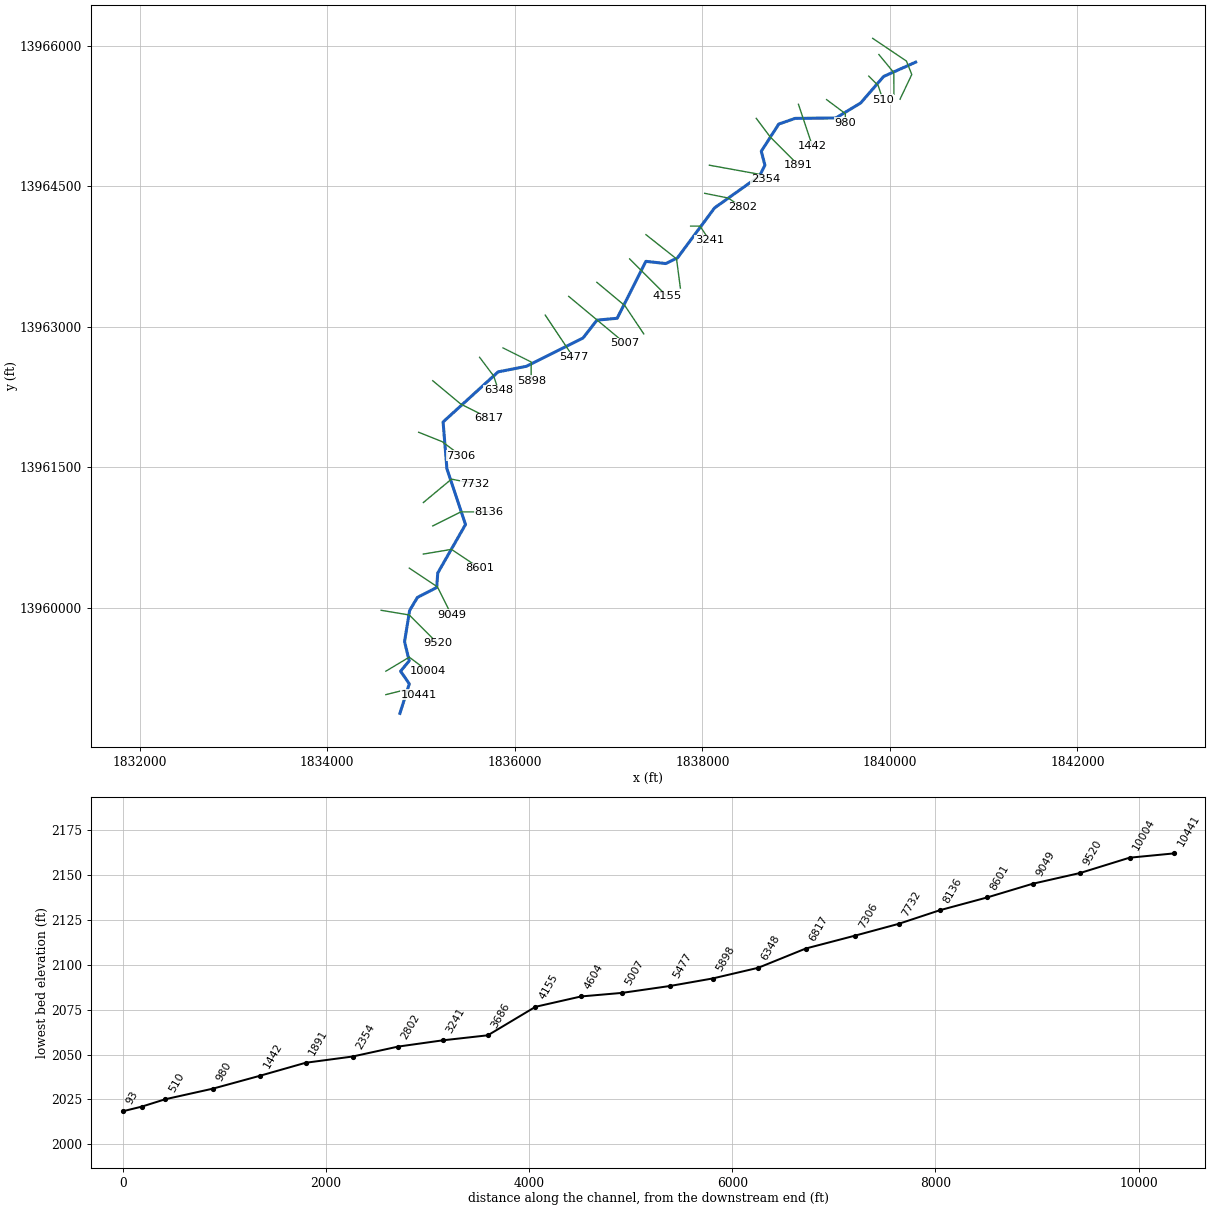
--- Stream0386.prj (project) ---

Proj Title=Stream0386 Base Level Engineering
Current Plan=p01
Default Exp/Contr=0.3,0.1
English Units
Geom File=g01
Flow File=f01
Plan File=p01
BEGIN DESCRIPTION:
Stream0386
END DESCRIPTION:

--- Stream0386.p01 (plan) ---

Plan Title=Multiple Run
Short Identifier=Multiple
Geom File=g01
Flow File=f01
Subcritical Flow
K Sum by GR= 0
Std Step Tol= 0.01
Critical Tol= 0.01
Num of Std Step Trials= 20
Max Error Tol= 0.3
Flow Tol Ratio= 0.001
Split Flow NTrial= 30
Split Flow Tol= 0.02
Split Flow Ratio= 0.02
Log Output Level= 0
Friction Slope Method= 1
Unsteady Friction Slope Method= 2
Unsteady Bridges Friction Slope Method= 1
Parabolic Critical Depth
Global Vel Dist=  1 , 1 , 1
Global Log Level= 0
CheckData=True
Encroach Param= -1, 0, 0, 0
BEGIN DESCRIPTION:
Multiple Run
END DESCRIPTION:

--- Stream0386.f01 (steady flow) ---

Flow Title=Multiple
Number of Profiles=7
Profile Names=10-year,25-year,50-year,1pct_min,100-year,1pct_plu,500-year
River Rch & RM= Stream0386,Reach-1,10441
     432     693     928     602    1201    2396    1984
River Rch & RM= Stream0386,Reach-1,7306
    1029    1747    2424    1626    3243    6471    5738
Boundary for River Rch & Prof#=Stream0386,Reach-1,1
Up Type=0
Dn Type=3
Dn Slope=0.005
Boundary for River Rch & Prof#=Stream0386,Reach-1,2
Up Type=0
Dn Type=3
Dn Slope=0.005
Boundary for River Rch & Prof#=Stream0386,Reach-1,3
Up Type=0
Dn Type=3
Dn Slope=0.005
Boundary for River Rch & Prof#=Stream0386,Reach-1,4
Up Type=0
Dn Type=3
Dn Slope=0.005
Boundary for River Rch & Prof#=Stream0386,Reach-1,5
Up Type=0
Dn Type=3
Dn Slope=0.005
Boundary for River Rch & Prof#=Stream0386,Reach-1,6
Up Type=0
Dn Type=3
Dn Slope=0.005
Boundary for River Rch & Prof#=Stream0386,Reach-1,7
Up Type=0
Dn Type=3
Dn Slope=0.005

--- Stream0386.g01 (geometry) ---

Geom Title=Existing Conditions

River Reach=Stream0386,Reach-1
Reach XY= 30
      1834775.00     13958875.00      1834874.97     13959190.42
      1834782.10     13959325.00      1834874.39     13959435.62
      1834824.53     13959640.16      1834878.75     13959973.45
      1834961.34     13960111.74      1835167.19     13960218.79
      1835178.76     13960373.44      1835474.63     13960890.27
      1835276.20     13961485.50      1835235.48     13961984.80
      1835822.57     13962519.48      1836123.44     13962578.76
      1836727.44     13962880.52      1836876.28     13963071.48
      1837091.70     13963091.37      1837398.11     13963698.99
      1837609.73     13963675.37      1837734.71     13963735.75
      1838130.62     13964269.38      1838611.39     13964611.79
      1838667.47     13964724.99      1838628.68     13964873.41
      1838815.19     13965164.49      1838990.22     13965224.48
      1839423.45     13965228.75      1839688.21     13965388.63
      1839933.34     13965671.84      1840275.00     13965825.00

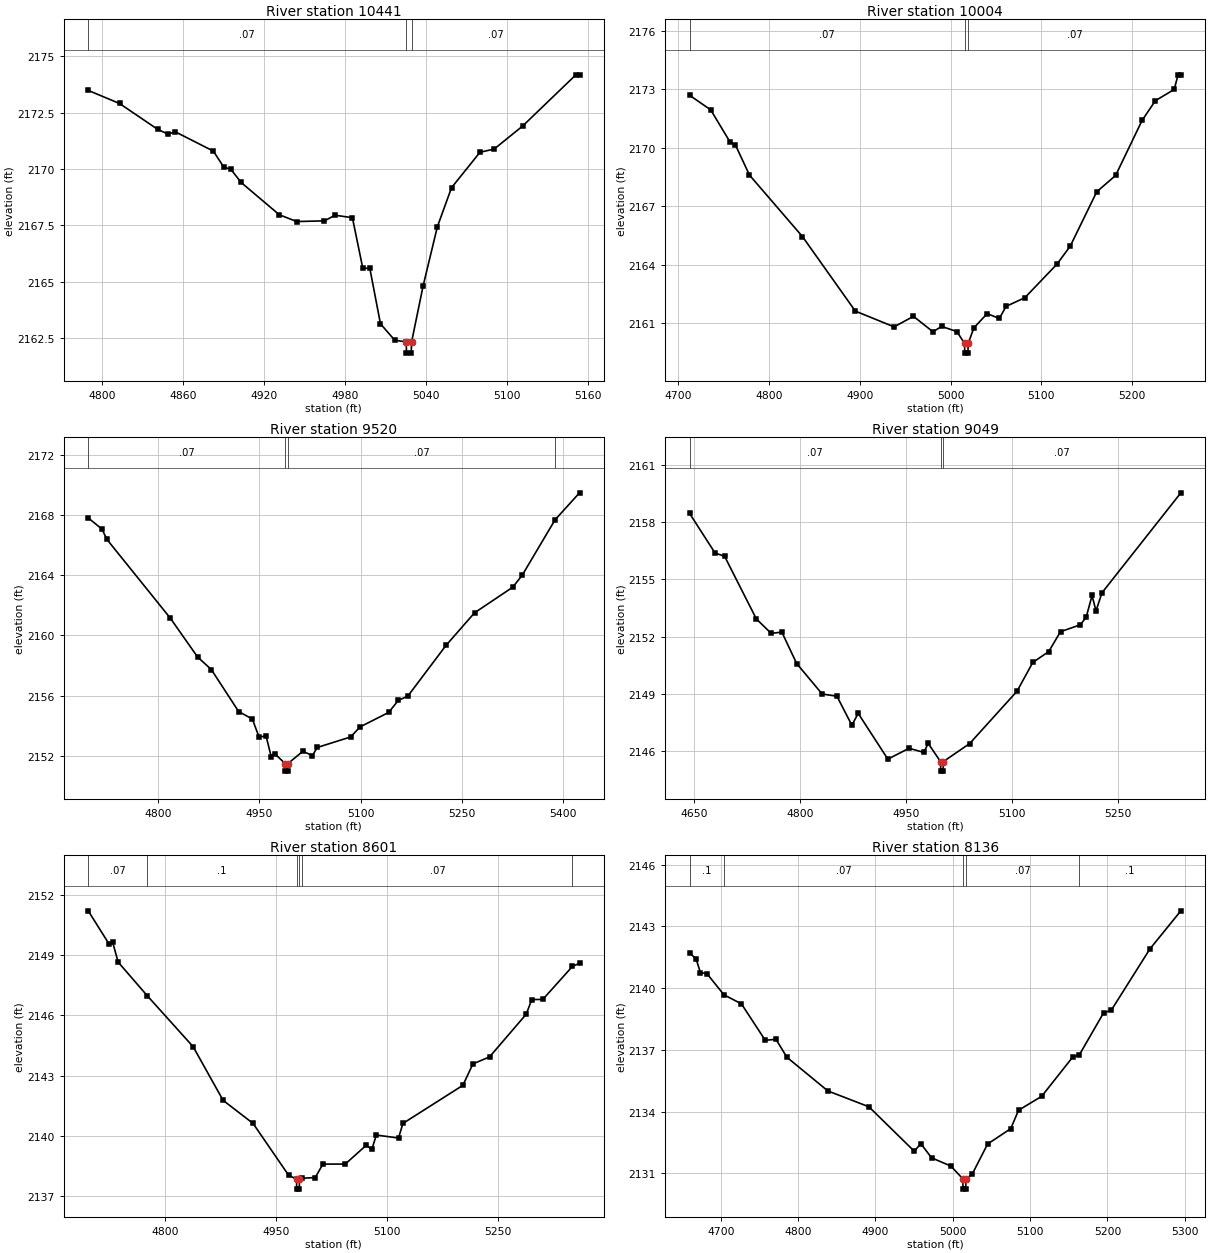
Type RM Length L Ch R = 1,10441,437,437,437
BEGIN DESCRIPTION:
Stream0386 23.0
END DESCRIPTION:
XS GIS Cut Line= 3
      1834624.98     13959075.00      1834825.00     13959125.00
      1834975.01     13959075.00
#Sta/Elev= 30
  4789.6 2173.48  4812.8 2172.90  4841.2 2171.75  4848.9 2171.54  4854.0 2171.65
  4882.4 2170.79  4890.1 2170.08  4895.3 2169.99  4903.0 2169.40  4931.3 2167.97
  4944.2 2167.67  4964.8 2167.70  4972.6 2167.95  4985.5 2167.84  4993.2 2165.60
  4998.4 2165.60  5006.3 2163.14  5016.9 2162.41  5025.4 2162.34  5025.6 2161.84
  5029.1 2161.84  5029.4 2162.34  5037.9 2164.81  5048.5 2167.44  5059.0 2169.17
  5080.1 2170.74  5090.6 2170.88  5111.7 2171.90  5151.2 2174.17  5153.9 2174.17
#Mann=3,-1,0
  4789.6    0.07       0  5025.4    0.05       0  5029.4    0.07       0
Bank Sta=5025.4,5029.4
Exp/Cntr=0.3,0.1

Type RM Length L Ch R = 1,10004,484,484,484
BEGIN DESCRIPTION:
Stream0386 22.0
END DESCRIPTION:
XS GIS Cut Line= 3
      1834625.03     13959325.02      1834875.00     13959475.00
      1835074.99     13959325.01
#Sta/Elev= 30
  4712.3 2172.70  4735.6 2171.95  4757.0 2170.29  4762.8 2170.15  4778.3 2168.60
  4836.7 2165.44  4895.0 2161.61  4937.7 2160.80  4959.1 2161.34  4980.5 2160.55
  4990.2 2160.82  5006.9 2160.56  5015.4 2159.95  5015.6 2159.45  5019.1 2159.45
  5019.4 2159.95  5025.7 2160.75  5040.3 2161.48  5053.8 2161.23  5061.1 2161.85
  5081.9 2162.30  5117.4 2164.03  5131.9 2164.95  5161.1 2167.74  5181.9 2168.58
  5211.1 2171.41  5225.7 2172.42  5246.5 2173.00  5250.7 2173.75  5253.8 2173.75
#Mann=3,-1,0
  4712.3    0.07       0  5015.4    0.05       0  5019.4    0.07       0
Bank Sta=5015.4,5019.4
Exp/Cntr=0.3,0.1

Type RM Length L Ch R = 1,9520,471,471,471
BEGIN DESCRIPTION:
Stream0386 21.0
END DESCRIPTION:
XS GIS Cut Line= 3
      1834575.03     13959975.00      1834875.00     13959925.00
      1835175.02     13959624.98
#Sta/Elev= 30
  4696.3 2167.80  4716.5 2167.07  4724.1 2166.37  4817.9 2161.15  4858.5 2158.56
  4878.8 2157.73  4919.3 2154.94  4939.6 2154.44  4949.7 2153.23  4959.9 2153.33
  4967.5 2151.95  4972.5 2152.15  4988.3 2151.48  4988.5 2150.98  4992.0 2150.98
  4992.3 2151.48  5014.6 2152.30  5028.7 2152.01  5035.8 2152.55  5085.3 2153.25
  5099.4 2153.92  5141.8 2154.88  5156.0 2155.68  5170.1 2155.96  5226.7 2159.33
  5269.1 2161.50  5325.7 2163.20  5339.8 2164.00  5388.5 2167.68  5424.7 2169.47
#Mann=4,-1,0
  4696.3    0.07       0  4988.3    0.05       0  4992.3    0.07       0
  5388.5     0.1       0
Bank Sta=4988.3,4992.3
Exp/Cntr=0.3,0.1

Type RM Length L Ch R = 1,9049,448,448,448
BEGIN DESCRIPTION:
Stream0386 20.0
END DESCRIPTION:
XS GIS Cut Line= 3
      1834875.00     13960425.00      1835175.00     13960225.00
      1835325.02     13959924.97
#Sta/Elev= 30
  4643.4 2158.47  4679.5 2156.39  4693.0 2156.22  4738.0 2152.93  4759.1 2152.17
  4774.1 2152.24  4795.1 2150.59  4831.2 2148.99  4852.2 2148.87  4873.3 2147.35
  4882.3 2147.97  4924.3 2145.57  4954.4 2146.14  4975.4 2145.92  4981.4 2146.40
  4998.9 2145.44  4999.2 2144.94  5002.7 2144.94  5002.9 2145.44  5040.3 2146.39
  5107.4 2149.14  5129.7 2150.65  5152.1 2151.21  5168.9 2152.26  5196.8 2152.62
  5205.2 2153.01  5213.6 2154.16  5219.2 2153.35  5227.6 2154.30  5339.4 2159.55
#Mann=3,-1,0
  4643.4    0.07       0  4998.9    0.05       0  5002.9    0.07       0
Bank Sta=4998.9,5002.9
Exp/Cntr=0.3,0.1

Type RM Length L Ch R = 1,8601,465,465,465
BEGIN DESCRIPTION:
Stream0386 19.0
END DESCRIPTION:
XS GIS Cut Line= 3
      1835025.01     13960575.00      1835325.00     13960625.00
      1835625.02     13960424.99
#Sta/Elev= 30
  4695.9 2151.22  4723.8 2149.58  4728.8 2149.67  4736.4 2148.66  4775.8 2146.98
  4837.8 2144.44  4878.4 2141.76  4918.9 2140.61  4967.1 2138.02  4977.7 2137.83
  4978.0 2137.33  4981.5 2137.33  4981.7 2137.83  4985.6 2137.87  5003.0 2137.91
  5013.5 2138.58  5043.6 2138.58  5072.1 2139.52  5079.6 2139.31  5085.7 2140.03
  5115.7 2139.88  5121.7 2140.61  5202.8 2142.51  5216.4 2143.58  5238.9 2143.93
  5288.5 2146.06  5296.0 2146.79  5311.0 2146.80  5351.1 2148.45  5360.6 2148.60
#Mann=6,-1,0
  4695.9    0.07       0  4775.8     0.1       0  4977.7    0.05       0
  4981.7     0.1       0  4985.6    0.07       0  5351.1     0.1       0
Bank Sta=4977.7,4981.7
Exp/Cntr=0.3,0.1

Type RM Length L Ch R = 1,8136,404,404,404
BEGIN DESCRIPTION:
Stream0386 18.0
END DESCRIPTION:
XS GIS Cut Line= 3
      1835124.96     13960874.98      1835425.00     13961025.00
      1835725.05     13961025.00
#Sta/Elev= 30
  4659.5 2141.71  4667.9 2141.43  4673.5 2140.76  4681.9 2140.71  4704.0 2139.68
  4726.6 2139.24  4757.4 2137.47  4771.3 2137.52  4785.3 2136.65  4838.4 2135.01
  4891.5 2134.24  4950.2 2132.08  4958.6 2132.45  4972.6 2131.76  4997.5 2131.36
  5013.0 2130.74  5013.2 2130.24  5016.7 2130.24  5017.0 2130.74  5025.0 2130.96
  5045.0 2132.43  5075.0 2133.18  5085.0 2134.07  5115.0 2134.75  5155.0 2136.65
  5163.8 2136.77  5195.0 2138.80  5205.0 2138.93  5255.0 2141.91  5295.0 2143.76
#Mann=5,-1,0
  4659.5     0.1       0  4704.0    0.07       0  5013.0    0.05       0
  5017.0    0.07       0  5163.8     0.1       0
Bank Sta=5013,5017
Exp/Cntr=0.3,0.1

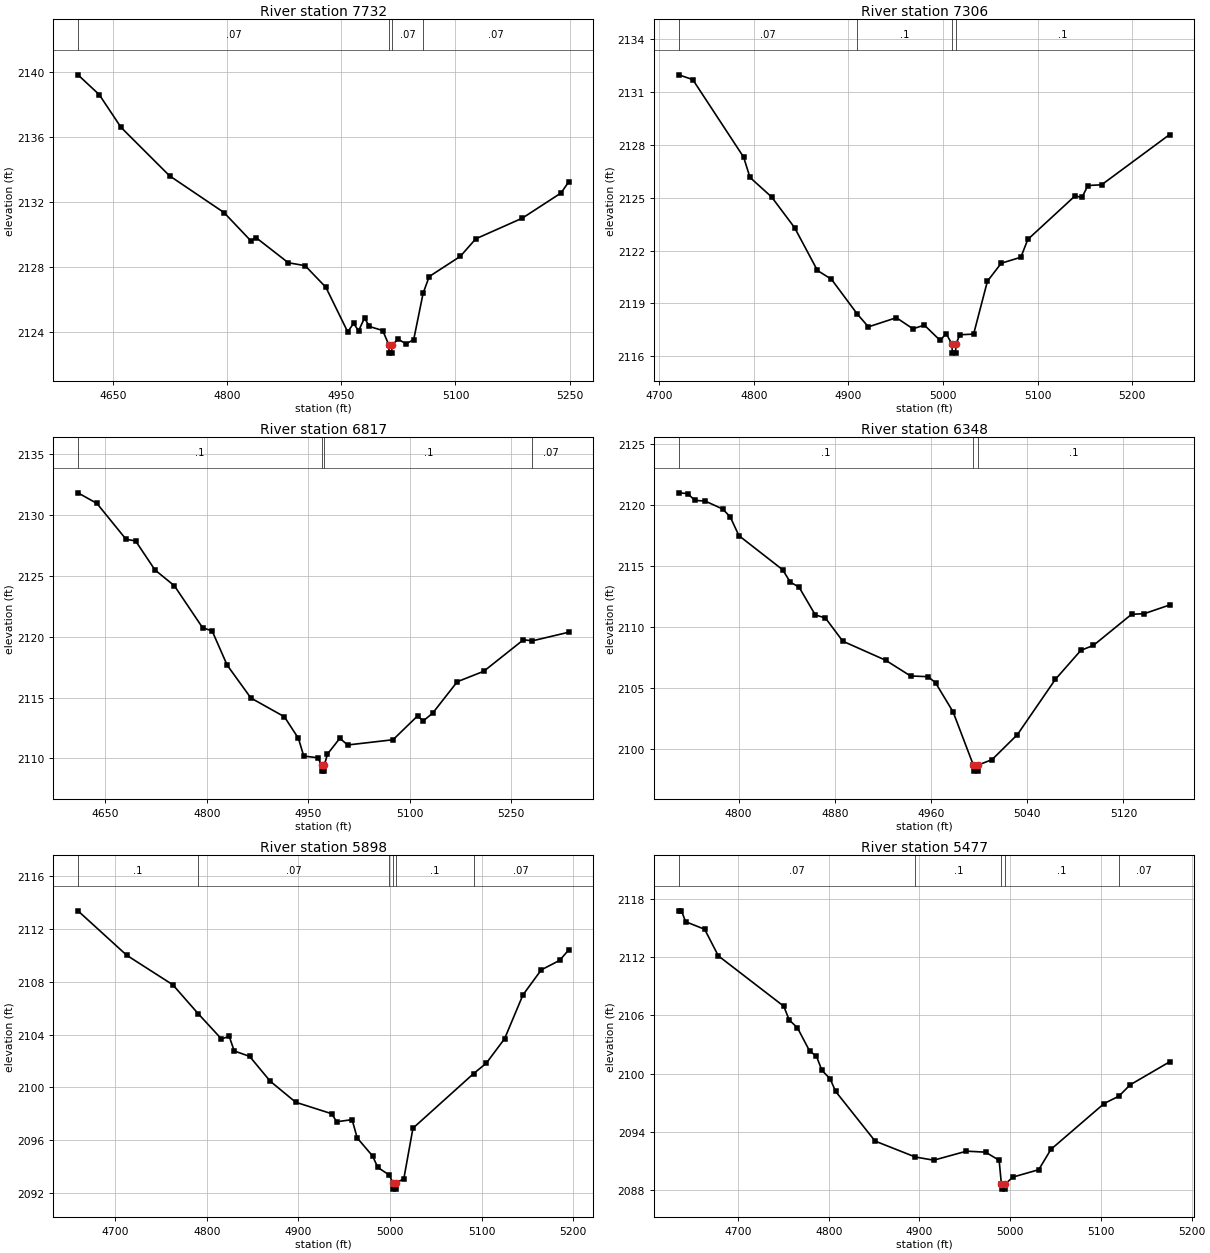
Type RM Length L Ch R = 1,7732,426,426,426
BEGIN DESCRIPTION:
Stream0386 17.0
END DESCRIPTION:
XS GIS Cut Line= 3
      1835025.03     13961125.02      1835325.00     13961375.00
      1835574.97     13961325.01
#Sta/Elev= 30
  4603.6 2139.81  4631.6 2138.59  4660.2 2136.58  4724.0 2133.60  4795.6 2131.34
  4830.7 2129.61  4837.9 2129.79  4880.2 2128.25  4902.3 2128.07  4929.6 2126.74
  4958.3 2124.00  4966.1 2124.52  4972.6 2124.06  4980.4 2124.85  4986.9 2124.33
  5004.3 2124.08  5012.5 2123.19  5012.7 2122.69  5016.2 2122.69  5016.5 2123.19
  5024.7 2123.55  5034.9 2123.26  5045.1 2123.52  5057.5 2126.38  5065.5 2127.40
  5106.3 2128.64  5126.7 2129.72  5187.8 2130.99  5238.8 2132.54  5249.0 2133.23
#Mann=4,-1,0
  4603.6    0.07       0  5012.5    0.05       0  5016.5    0.07       0
  5057.5    0.07       0
Bank Sta=5012.5,5016.5
Exp/Cntr=0.3,0.1

Type RM Length L Ch R = 1,7306,489,489,489
BEGIN DESCRIPTION:
Stream0386 16.0
END DESCRIPTION:
XS GIS Cut Line= 3
      1834975.04     13961874.98      1835225.00     13961775.00
      1835424.99     13961625.01
#Sta/Elev= 30
  4720.5 2131.97  4735.3 2131.70  4789.1 2127.30  4795.8 2126.15  4818.7 2125.04
  4843.0 2123.30  4867.2 2120.87  4882.0 2120.37  4909.3 2118.40  4921.1 2117.67
  4950.7 2118.19  4968.2 2117.56  4980.3 2117.77  4997.0 2116.90  5003.3 2117.29
  5009.6 2116.68  5009.8 2116.18  5013.3 2116.18  5013.6 2116.68  5017.8 2117.22
  5032.4 2117.26  5047.0 2120.26  5061.6 2121.28  5082.4 2121.62  5089.7 2122.63
  5139.7 2125.10  5147.0 2125.01  5153.3 2125.69  5167.8 2125.73  5239.7 2128.58
#Mann=4,-1,0
  4720.5    0.07       0  4909.3     0.1       0  5009.6    0.05       0
  5013.6     0.1       0
Bank Sta=5009.6,5013.6
Exp/Cntr=0.3,0.1

Type RM Length L Ch R = 1,6817,469,469,469
BEGIN DESCRIPTION:
Stream0386 15.0
END DESCRIPTION:
XS GIS Cut Line= 3
      1835124.99     13962425.01      1835425.00     13962175.00
      1835724.97     13962025.02
#Sta/Elev= 30
  4609.5 2131.84  4637.5 2130.97  4680.5 2128.03  4694.8 2127.88  4723.4 2125.50
  4752.1 2124.20  4793.7 2120.76  4808.0 2120.48  4830.2 2117.67  4865.3 2114.97
  4914.8 2113.43  4935.6 2111.65  4943.4 2110.20  4964.2 2110.06  4970.0 2109.46
  4970.3 2108.96  4973.8 2108.96  4974.0 2109.46  4978.5 2110.36  4996.8 2111.66
  5008.4 2111.11  5075.5 2111.54  5111.8 2113.50  5120.2 2113.09  5134.2 2113.73
  5170.5 2116.31  5209.7 2117.17  5268.4 2119.76  5281.5 2119.67  5335.4 2120.38
#Mann=4,-1,0
  4609.5     0.1       0  4970.0    0.05       0  4974.0     0.1       0
  5281.5    0.07       0
Bank Sta=4970,4974
Exp/Cntr=0.3,0.1

Type RM Length L Ch R = 1,6348,450,450,450
BEGIN DESCRIPTION:
Stream0386 14.0
END DESCRIPTION:
XS GIS Cut Line= 3
      1835625.01     13962674.98      1835775.00     13962475.00
      1835825.00     13962324.99
#Sta/Elev= 30
  4750.3 2120.98  4757.6 2120.92  4763.8 2120.36  4772.2 2120.31  4786.7 2119.66
  4793.0 2119.03  4800.3 2117.48  4836.7 2114.69  4843.0 2113.68  4850.3 2113.27
  4863.8 2111.00  4872.2 2110.75  4886.7 2108.85  4922.2 2107.30  4943.0 2106.01
  4957.6 2105.95  4963.8 2105.45  4978.4 2103.07  4995.2 2098.73  4995.4 2098.23
  4998.9 2098.23  4999.2 2098.73  5010.8 2099.17  5031.9 2101.22  5063.5 2105.74
  5084.6 2108.10  5095.1 2108.51  5126.8 2111.05  5137.3 2111.10  5158.4 2111.81
#Mann=3,-1,0
  4750.3     0.1       0  4995.2    0.05       0  4999.2     0.1       0
Bank Sta=4995.2,4999.2
Exp/Cntr=0.3,0.1

Type RM Length L Ch R = 1,5898,421,421,421
BEGIN DESCRIPTION:
Stream0386 13.0
END DESCRIPTION:
XS GIS Cut Line= 3
      1835874.96     13962775.02      1836175.00     13962625.00
      1836175.00     13962424.95
#Sta/Elev= 30
  4659.5 2113.39  4712.7 2110.02  4763.0 2107.78  4790.9 2105.57  4816.1 2103.67
  4824.5 2103.87  4830.0 2102.76  4846.8 2102.35  4869.2 2100.47  4897.1 2098.87
  4936.3 2098.00  4941.8 2097.39  4958.6 2097.55  4964.2 2096.16  4981.0 2094.79
  4986.6 2093.93  4999.1 2093.35  5003.0 2092.78  5003.2 2092.28  5006.7 2092.28
  5007.0 2092.78  5015.0 2093.05  5025.0 2096.90  5091.1 2101.04  5105.0 2101.83
  5125.0 2103.69  5145.0 2107.01  5165.0 2108.91  5185.0 2109.63  5195.0 2110.43
#Mann=6,-1,0
  4659.5     0.1       0  4790.9    0.07       0  4999.1     0.1       0
  5003.0    0.05       0  5007.0     0.1       0  5091.1    0.07       0
Bank Sta=5003,5007
Exp/Cntr=0.3,0.1

Type RM Length L Ch R = 1,5477,470,470,470
BEGIN DESCRIPTION:
Stream0386 12.0
END DESCRIPTION:
XS GIS Cut Line= 3
      1836325.00     13963125.00      1836525.00     13962825.00
      1836624.98     13962675.02
#Sta/Elev= 30
  4634.8 2116.77  4637.8 2116.77  4642.3 2115.65  4663.3 2114.87  4678.4 2112.13
  4750.5 2106.94  4756.5 2105.52  4765.5 2104.73  4779.0 2102.32  4786.5 2101.79
  4792.5 2100.34  4801.6 2099.46  4807.6 2098.17  4851.1 2093.05  4895.4 2091.41
  4915.7 2091.08  4951.8 2092.01  4972.8 2091.91  4987.8 2091.07  4990.3 2088.60
  4990.6 2088.10  4994.1 2088.10  4994.3 2088.60  5002.9 2089.34  5031.4 2090.10
  5044.9 2092.20  5103.5 2096.92  5119.8 2097.68  5132.1 2098.84  5175.6 2101.21
#Mann=5,-1,0
  4634.8    0.07       0  4895.4     0.1       0  4990.3    0.05       0
  4994.3     0.1       0  5119.8    0.07       0
Bank Sta=4990.3,4994.3
Exp/Cntr=0.3,0.1

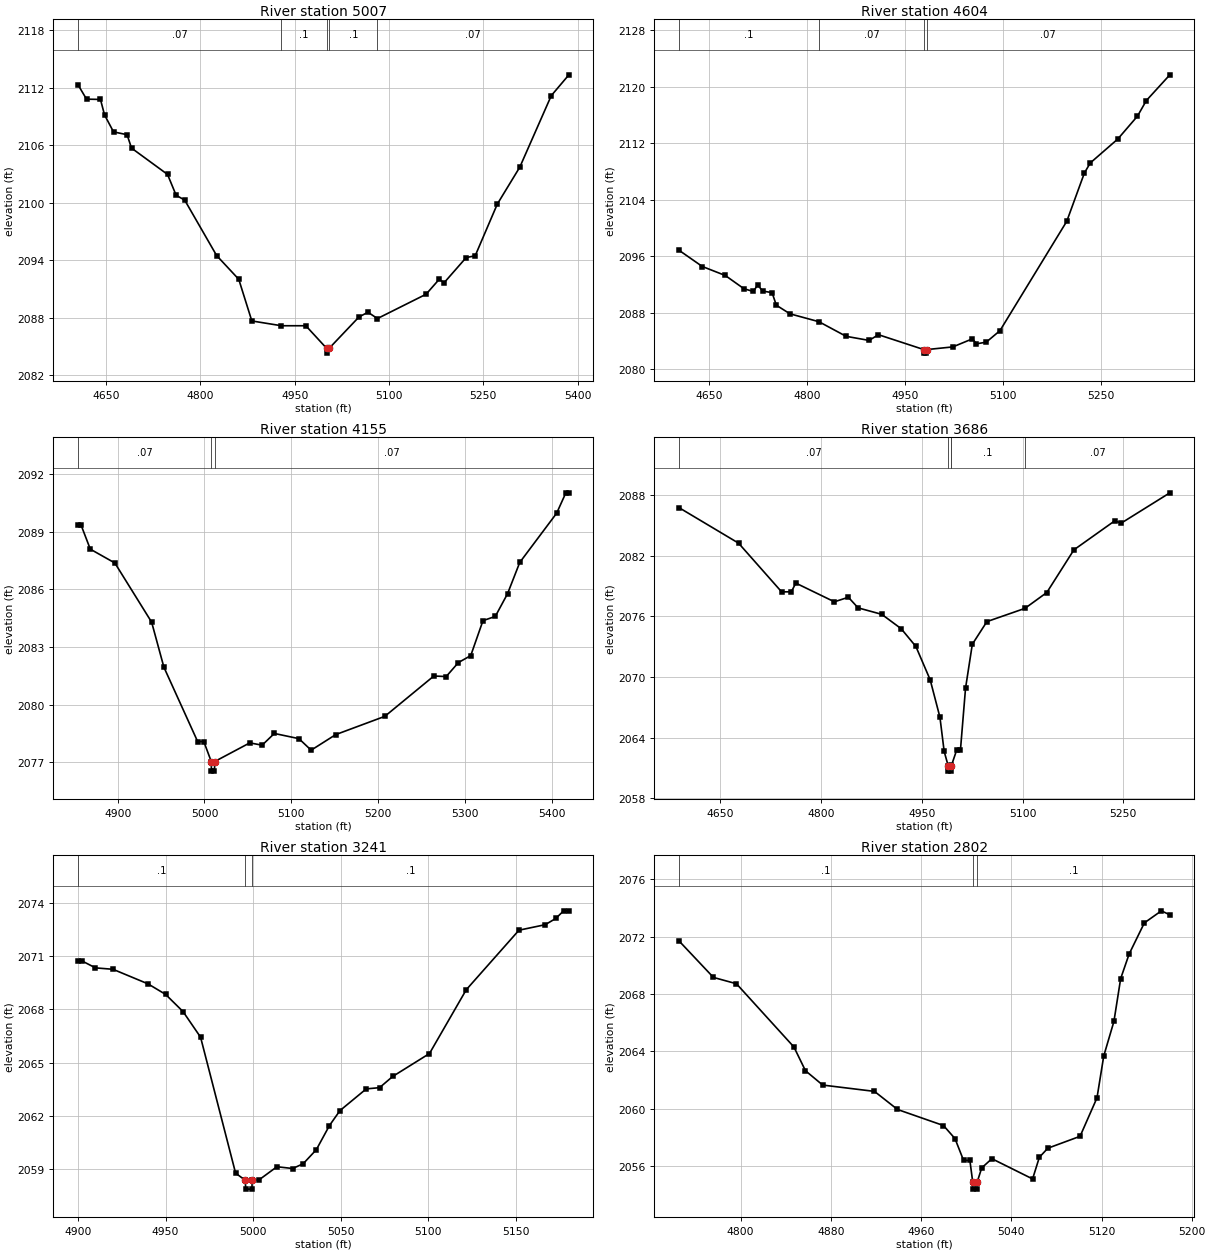
Type RM Length L Ch R = 1,5007,403,403,403
BEGIN DESCRIPTION:
Stream0386 11.0
END DESCRIPTION:
XS GIS Cut Line= 3
      1836575.02     13963324.98      1836875.00     13963075.00
      1837175.01     13962825.00
#Sta/Elev= 30
  4605.1 2112.31  4618.7 2110.80  4640.9 2110.77  4647.4 2109.15  4661.7 2107.38
  4683.2 2107.09  4690.3 2105.69  4747.6 2102.94  4761.3 2100.76  4774.9 2100.26
  4825.7 2094.47  4860.9 2091.99  4881.7 2087.64  4928.8 2087.14  4967.6 2087.14
  5000.7 2084.78  5001.0 2084.28  5004.7 2084.78  5052.2 2088.06  5066.5 2088.55
  5081.5 2087.89  5158.9 2090.43  5179.8 2091.99  5187.6 2091.63  5222.7 2094.26
  5237.0 2094.44  5272.2 2099.84  5308.0 2103.70  5358.1 2111.17  5386.1 2113.34
#Mann=5,-1,0
  4605.1    0.07       0  4928.8     0.1       0  5000.7    0.05       0
  5004.7     0.1       0  5081.5    0.07       0
Bank Sta=5000.7,5004.7
Exp/Cntr=0.3,0.1

Type RM Length L Ch R = 1,4604,449,449,449
BEGIN DESCRIPTION:
Stream0386 10.0
END DESCRIPTION:
XS GIS Cut Line= 3
      1836875.03     13963474.98      1837175.00     13963225.00
      1837374.98     13962925.03
#Sta/Elev= 30
  4603.8 2096.88  4639.6 2094.57  4674.7 2093.30  4703.3 2091.42  4717.7 2091.03
  4724.2 2091.95  4732.0 2091.09  4746.3 2090.87  4752.8 2089.09  4773.6 2087.87
  4818.0 2086.75  4859.6 2084.68  4894.7 2084.10  4909.0 2084.91  4978.6 2082.80
  4978.9 2082.30  4982.4 2082.30  4982.6 2082.80  5022.8 2083.18  5052.9 2084.33
  5058.9 2083.62  5073.9 2083.85  5094.9 2085.48  5197.1 2100.97  5224.1 2107.82
  5233.1 2109.24  5275.2 2112.63  5305.3 2115.87  5318.8 2118.07  5354.8 2121.72
#Mann=4,-1,0
  4603.8     0.1       0  4818.0    0.07       0  4978.6    0.05       0
  4982.6    0.07       0
Bank Sta=4978.6,4982.6
Exp/Cntr=0.3,0.1

Type RM Length L Ch R = 1,4155,469,469,469
BEGIN DESCRIPTION:
Stream0386 9.0
END DESCRIPTION:
XS GIS Cut Line= 3
      1837224.98     13963725.02      1837325.00     13963625.00
      1837624.99     13963325.01
#Sta/Elev= 30
  4854.2 2089.34  4857.8 2089.34  4868.4 2088.09  4896.7 2087.37  4939.1 2084.29
  4953.2 2081.95  4992.1 2078.08  4999.2 2078.08  5007.8 2077.04  5008.0 2076.54
  5011.5 2076.54  5011.8 2077.04  5052.2 2078.01  5066.4 2077.89  5080.5 2078.50
  5108.8 2078.23  5122.9 2077.63  5151.2 2078.44  5207.8 2079.39  5264.3 2081.49
  5278.5 2081.46  5292.6 2082.19  5306.8 2082.55  5320.9 2084.37  5335.1 2084.59
  5349.2 2085.77  5363.3 2087.40  5405.8 2089.96  5416.4 2091.02  5419.9 2091.02
#Mann=3,-1,0
  4854.2    0.07       0  5007.8    0.05       0  5011.8    0.07       0
Bank Sta=5007.8,5011.8
Exp/Cntr=0.3,0.1

Type RM Length L Ch R = 1,3686,445,445,445
BEGIN DESCRIPTION:
Stream0386 8.0
END DESCRIPTION:
XS GIS Cut Line= 3
      1837398.67     13963983.79      1837725.00     13963725.00
      1837765.79     13963413.45
#Sta/Elev= 30
  4588.6 2086.77  4677.4 2083.25  4741.5 2078.43  4755.9 2078.44  4762.6 2079.30
  4820.0 2077.45  4840.8 2077.90  4855.3 2076.85  4890.5 2076.21  4919.4 2074.79
  4941.3 2073.03  4962.6 2069.73  4977.1 2066.03  4983.4 2062.65  4989.5 2061.20
  4989.7 2060.70  4993.2 2060.70  4993.5 2061.20  4994.3 2061.27  5001.9 2062.76
  5007.6 2062.76  5015.2 2068.90  5025.3 2073.25  5047.0 2075.49  5103.6 2076.80
  5136.2 2078.37  5176.5 2082.59  5237.1 2085.45  5247.1 2085.24  5319.3 2088.23
#Mann=5,-1,0
  4588.6    0.07       0  4989.5    0.05       0  4993.5    0.07       0
  4994.3     0.1       0  5103.6    0.07       0
Bank Sta=4989.5,4993.5
Exp/Cntr=0.3,0.1

Type RM Length L Ch R = 1,3241,439,439,439
BEGIN DESCRIPTION:
Stream0386 7.0
END DESCRIPTION:
XS GIS Cut Line= 3
      1837874.95     13964075.00      1837975.00     13964075.00
      1838074.99     13963925.02
#Sta/Elev= 30
  4900.0 2070.72  4902.5 2070.72  4910.0 2070.34  4920.0 2070.26  4940.0 2069.44
  4950.0 2068.85  4960.0 2067.88  4970.0 2066.44  4990.0 2058.79  4995.5 2058.39
  4995.8 2057.89  4999.3 2057.89  4999.5 2058.39  5003.1 2058.39  5013.6 2059.15
  5022.6 2059.05  5028.6 2059.32  5036.1 2060.11  5043.6 2061.47  5049.6 2062.31
  5064.6 2063.53  5072.2 2063.60  5079.7 2064.23  5100.7 2065.52  5121.7 2069.11
  5151.8 2072.46  5166.8 2072.77  5172.8 2073.12  5177.3 2073.55  5180.3 2073.55
#Mann=3,-1,0
  4900.0     0.1       0  4995.5    0.05       0  4999.5     0.1       0
Bank Sta=4995.5,4999.5
Exp/Cntr=0.3,0.1

Type RM Length L Ch R = 1,2802,448,448,448
BEGIN DESCRIPTION:
Stream0386 6.0
END DESCRIPTION:
XS GIS Cut Line= 3
      1838024.96     13964425.01      1838275.00     13964375.00
      1838425.02     13964274.99
#Sta/Elev= 30
  4745.3 2071.71  4775.9 2069.16  4796.3 2068.72  4847.3 2064.31  4857.5 2062.66
  4872.8 2061.66  4918.7 2061.22  4939.1 2059.96  4979.9 2058.84  4990.1 2057.93
  4997.7 2056.41  5003.3 2056.41  5005.8 2054.91  5006.1 2054.41  5009.6 2054.41
  5009.8 2054.91  5013.8 2055.89  5022.8 2056.53  5058.9 2055.12  5064.9 2056.63
  5072.4 2057.26  5101.0 2058.09  5116.0 2060.77  5122.0 2063.69  5131.0 2066.09
  5137.0 2069.08  5144.5 2070.79  5158.0 2072.96  5173.1 2073.80  5180.6 2073.52
#Mann=3,-1,0
  4745.3     0.1       0  5005.8    0.05       0  5009.8     0.1       0
Bank Sta=5005.8,5009.8
Exp/Cntr=0.3,0.1

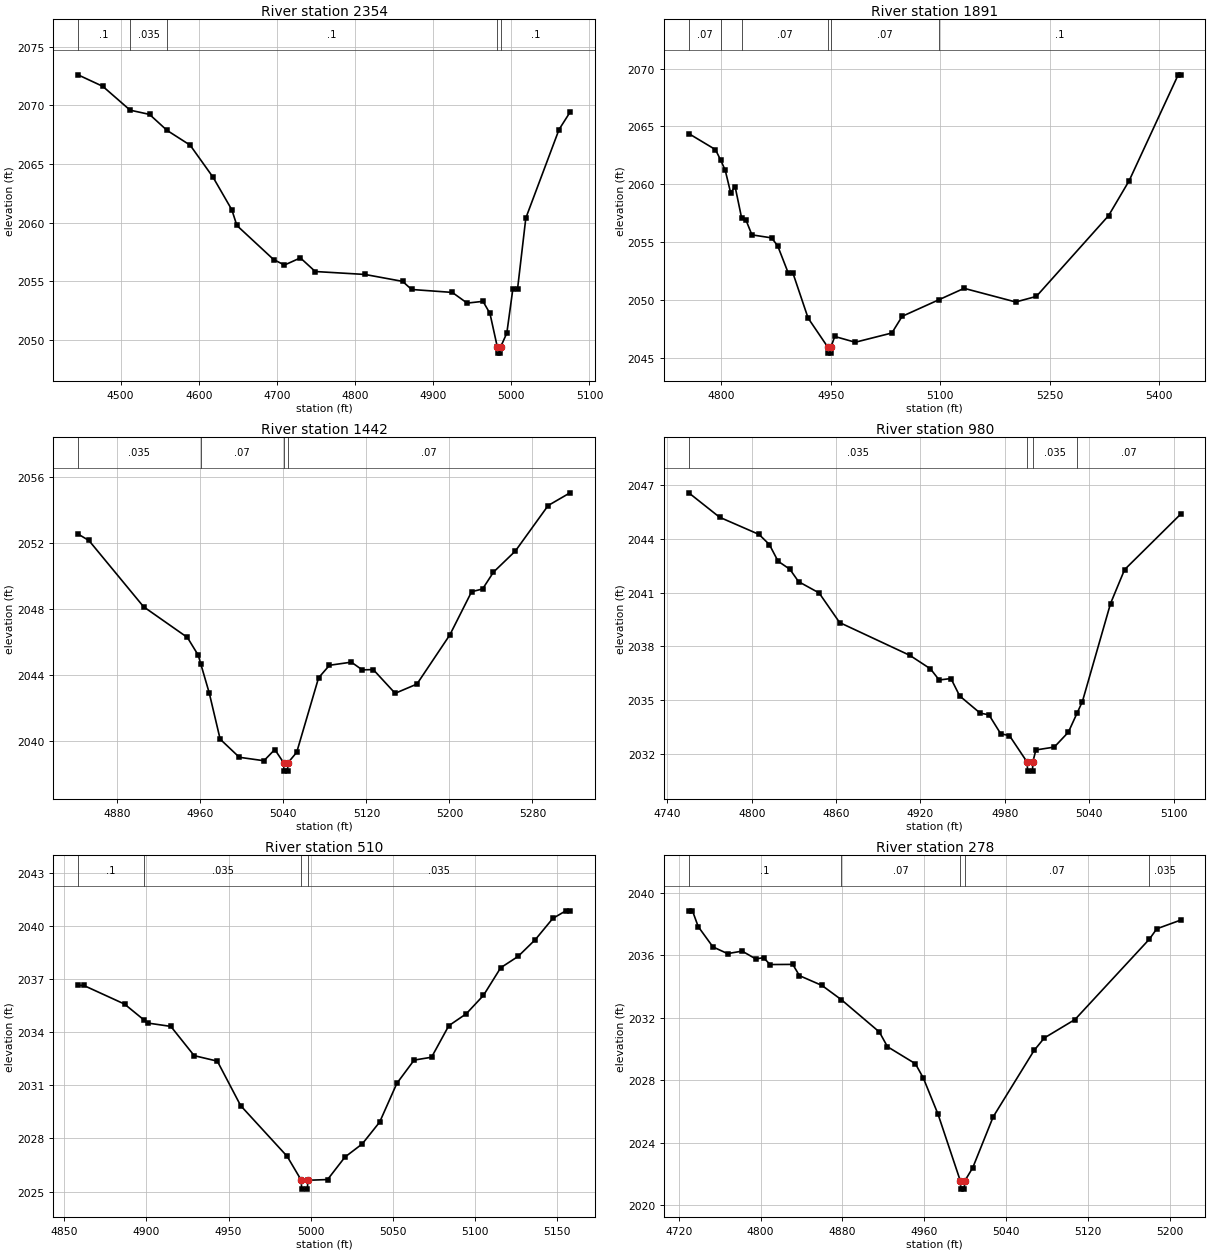
Type RM Length L Ch R = 1,2354,463,463,463
BEGIN DESCRIPTION:
Stream0386 5.0
END DESCRIPTION:
XS GIS Cut Line= 3
      1838075.02     13964725.00      1838625.00     13964625.00
      1838674.99     13964575.01
#Sta/Elev= 30
  4445.4 2072.59  4477.1 2071.61  4512.1 2069.58  4536.9 2069.22  4559.3 2067.86
  4588.9 2066.60  4618.2 2063.87  4642.3 2061.09  4648.7 2059.76  4695.7 2056.86
  4709.6 2056.39  4730.0 2057.00  4749.0 2055.84  4812.6 2055.59  4860.8 2055.00
  4872.3 2054.31  4924.4 2054.06  4943.4 2053.15  4963.7 2053.30  4972.6 2052.27
  4982.1 2049.39  4982.3 2048.89  4985.8 2048.89  4986.1 2049.39  4994.2 2050.60
  5001.9 2054.35  5007.9 2054.35  5018.5 2060.39  5061.0 2067.93  5075.1 2069.41
#Mann=5,-1,0
  4445.4     0.1       0  4512.1   0.035       0  4559.3     0.1       0
  4982.1    0.05       0  4986.1     0.1       0
Bank Sta=4982.1,4986.1
Exp/Cntr=0.3,0.1

Type RM Length L Ch R = 1,1891,449,449,449
BEGIN DESCRIPTION:
Stream0386 4.0
END DESCRIPTION:
XS GIS Cut Line= 3
      1838575.00     13965225.00      1838725.00     13965025.00
      1839025.03     13964724.97
#Sta/Elev= 30
  4755.5 2064.38  4792.0 2063.00  4799.2 2062.09  4805.5 2061.20  4812.8 2059.28
  4819.0 2059.79  4828.0 2057.06  4833.6 2056.95  4842.0 2055.63  4869.0 2055.37
  4877.4 2054.67  4892.0 2052.30  4898.2 2052.33  4919.0 2048.44  4946.2 2045.91
  4946.5 2045.41  4950.0 2045.41  4950.2 2045.91  4955.5 2046.85  4983.6 2046.35
  5033.8 2047.15  5047.9 2048.59  5098.5 2050.03  5132.8 2051.01  5203.5 2049.83
  5231.8 2050.31  5330.8 2057.29  5359.0 2060.31  5426.2 2069.46  5429.8 2069.46
#Mann=6,-1,0
  4755.5    0.07       0  4799.2   0.035       0  4828.0    0.07       0
  4946.2    0.05       0  4950.2    0.07       0  5098.5     0.1       0
Bank Sta=4946.2,4950.2
Exp/Cntr=0.3,0.1

Type RM Length L Ch R = 1,1442,462,462,462
BEGIN DESCRIPTION:
Stream0386 3.0
END DESCRIPTION:
XS GIS Cut Line= 3
      1839025.01     13965374.98      1839075.00     13965225.00
      1839174.99     13964925.02
#Sta/Elev= 30
  4842.0 2052.57  4852.5 2052.18  4905.2 2048.16  4947.4 2046.30  4957.9 2045.22
  4960.3 2044.70  4968.5 2042.93  4979.0 2040.13  4997.5 2039.03  5021.2 2038.82
  5031.7 2039.50  5040.3 2038.69  5040.5 2038.19  5044.0 2038.19  5044.3 2038.69
  5052.8 2039.33  5073.9 2043.85  5084.4 2044.61  5105.5 2044.80  5116.0 2044.33
  5126.6 2044.35  5147.7 2042.91  5168.7 2043.47  5200.4 2046.45  5221.4 2049.07
  5232.0 2049.24  5242.5 2050.26  5263.6 2051.54  5295.2 2054.30  5316.3 2055.07
#Mann=4,-1,0
  4842.0   0.035       0  4960.3    0.07       0  5040.3    0.05       0
  5044.3    0.07       0
Bank Sta=5040.3,5044.3
Exp/Cntr=0.3,0.1

Type RM Length L Ch R = 1,980,470,470,470
BEGIN DESCRIPTION:
Stream0386 2.0
END DESCRIPTION:
XS GIS Cut Line= 3
      1839325.00     13965425.00      1839525.00     13965275.00
      1839525.00     13965175.00
#Sta/Elev= 30
  4755.2 2046.56  4777.1 2045.20  4805.2 2044.24  4812.5 2043.68  4818.7 2042.75
  4827.1 2042.30  4833.3 2041.61  4847.9 2040.98  4862.5 2039.33  4912.5 2037.50
  4927.1 2036.75  4933.3 2036.13  4941.7 2036.21  4947.9 2035.24  4962.5 2034.28
  4968.7 2034.19  4977.1 2033.13  4983.3 2033.03  4995.9 2031.55  4996.2 2031.05
  4999.7 2031.05  4999.9 2031.55  5002.1 2032.23  5015.2 2032.39  5025.2 2033.22
  5031.5 2034.30  5035.2 2034.93  5055.2 2040.39  5065.2 2042.28  5105.2 2045.38
#Mann=4,-1,0
  4755.2   0.035       0  4995.9   0.035       0  4999.9   0.035       0
  5031.5    0.07       0
Bank Sta=4995.9,4999.9
Exp/Cntr=0.3,0.1

Type RM Length L Ch R = 1,510,232,232,232
BEGIN DESCRIPTION:
Stream0386 1.0
END DESCRIPTION:
XS GIS Cut Line= 3
      1839775.02     13965674.98      1839875.00     13965575.00
      1839925.00     13965425.01
#Sta/Elev= 30
  4858.4 2036.63  4861.9 2036.63  4886.7 2035.58  4898.6 2034.68  4900.8 2034.51
  4914.9 2034.32  4929.1 2032.67  4943.2 2032.36  4957.4 2029.85  4985.7 2026.99
  4994.3 2025.64  4994.5 2025.14  4998.0 2025.14  4998.3 2025.64  5010.3 2025.68
  5020.9 2026.95  5031.4 2027.69  5042.0 2028.92  5052.5 2031.11  5063.0 2032.42
  5073.6 2032.58  5084.1 2034.36  5094.7 2035.03  5105.2 2036.07  5115.7 2037.63
  5126.3 2038.27  5136.8 2039.22  5147.4 2040.41  5155.3 2040.84  5157.9 2040.84
#Mann=4,-1,0
  4858.4     0.1       0  4898.6   0.035       0  4994.3   0.035       0
  4998.3   0.035       0
Bank Sta=4994.3,4998.3
Exp/Cntr=0.3,0.1

Type RM Length L Ch R = 1,278,185,185,185
BEGIN DESCRIPTION:
Stream0386 0.0
END DESCRIPTION:
XS GIS Cut Line= 3
      1839882.87     13965905.58      1840042.09     13965712.40
      1840043.28     13965481.54
#Sta/Elev= 30
  4729.7 2038.85  4733.3 2038.85  4738.9 2037.84  4753.3 2036.54  4767.6 2036.11
  4781.9 2036.27  4795.2 2035.77  4802.8 2035.85  4809.2 2035.41  4831.4 2035.42
  4837.9 2034.70  4860.0 2034.07  4878.9 2033.16  4916.1 2031.09  4924.0 2030.15
  4951.3 2029.06  4959.1 2028.14  4973.5 2025.82  4995.4 2021.53  4995.7 2021.03
  4999.2 2021.03  4999.4 2021.53  5007.4 2022.40  5027.4 2025.66  5067.4 2029.91
  5077.4 2030.71  5107.4 2031.89  5180.2 2037.04  5187.4 2037.70  5210.9 2038.26
#Mann=5,-1,0
  4729.7     0.1       0  4878.9    0.07       0  4995.4    0.05       0
  4999.4    0.07       0  5180.2   0.035       0
Bank Sta=4995.4,4999.4
Exp/Cntr=0.3,0.1

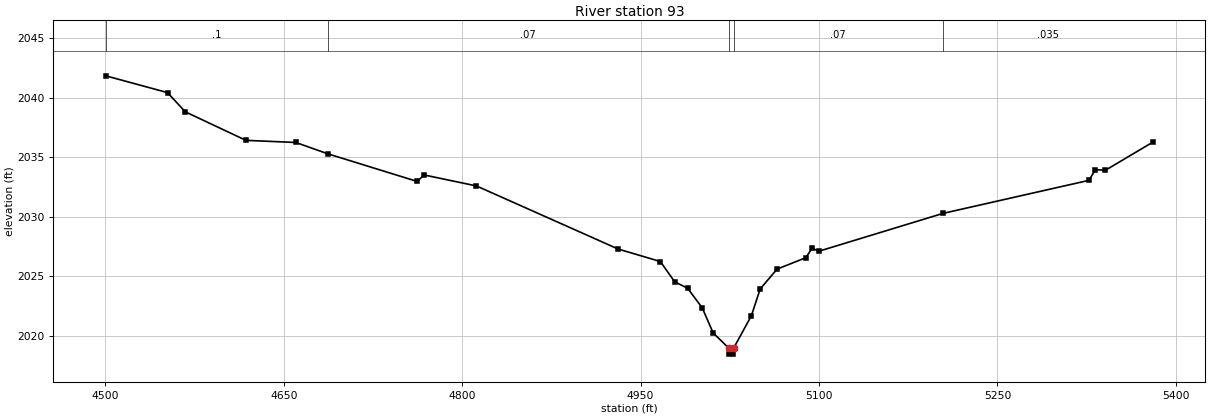
Type RM Length L Ch R = 1,93,0,0,0
BEGIN DESCRIPTION:
Stream0386 0.1
END DESCRIPTION:
XS GIS Cut Line= 4
      1839816.70     13966078.79      1840176.92     13965835.75
      1840233.34     13965692.52      1840108.01     13965428.88
#Sta/Elev= 30
  4500.4 2041.85  4552.3 2040.44  4567.2 2038.83  4618.2 2036.43  4660.2 2036.25
  4687.0 2035.30  4762.1 2032.98  4768.1 2033.52  4812.0 2032.60  4931.1 2027.30
  4966.6 2026.25  4978.7 2024.54  4989.5 2024.01  5001.8 2022.36  5011.0 2020.25
  5024.2 2018.97  5024.4 2018.47  5027.9 2018.47  5028.2 2018.97  5043.2 2021.71
  5050.5 2023.94  5064.7 2025.61  5088.9 2026.57  5094.2 2027.37  5099.7 2027.11
  5204.1 2030.29  5326.9 2033.07  5332.4 2033.97  5340.8 2033.92  5380.8 2036.29
#Mann=5,-1,0
  4500.4     0.1       0  4687.0    0.07       0  5024.2    0.05       0
  5028.2    0.07       0  5204.1   0.035       0
Bank Sta=5024.2,5028.2
Exp/Cntr=0.3,0.1

Chan Stop Cuts=-1