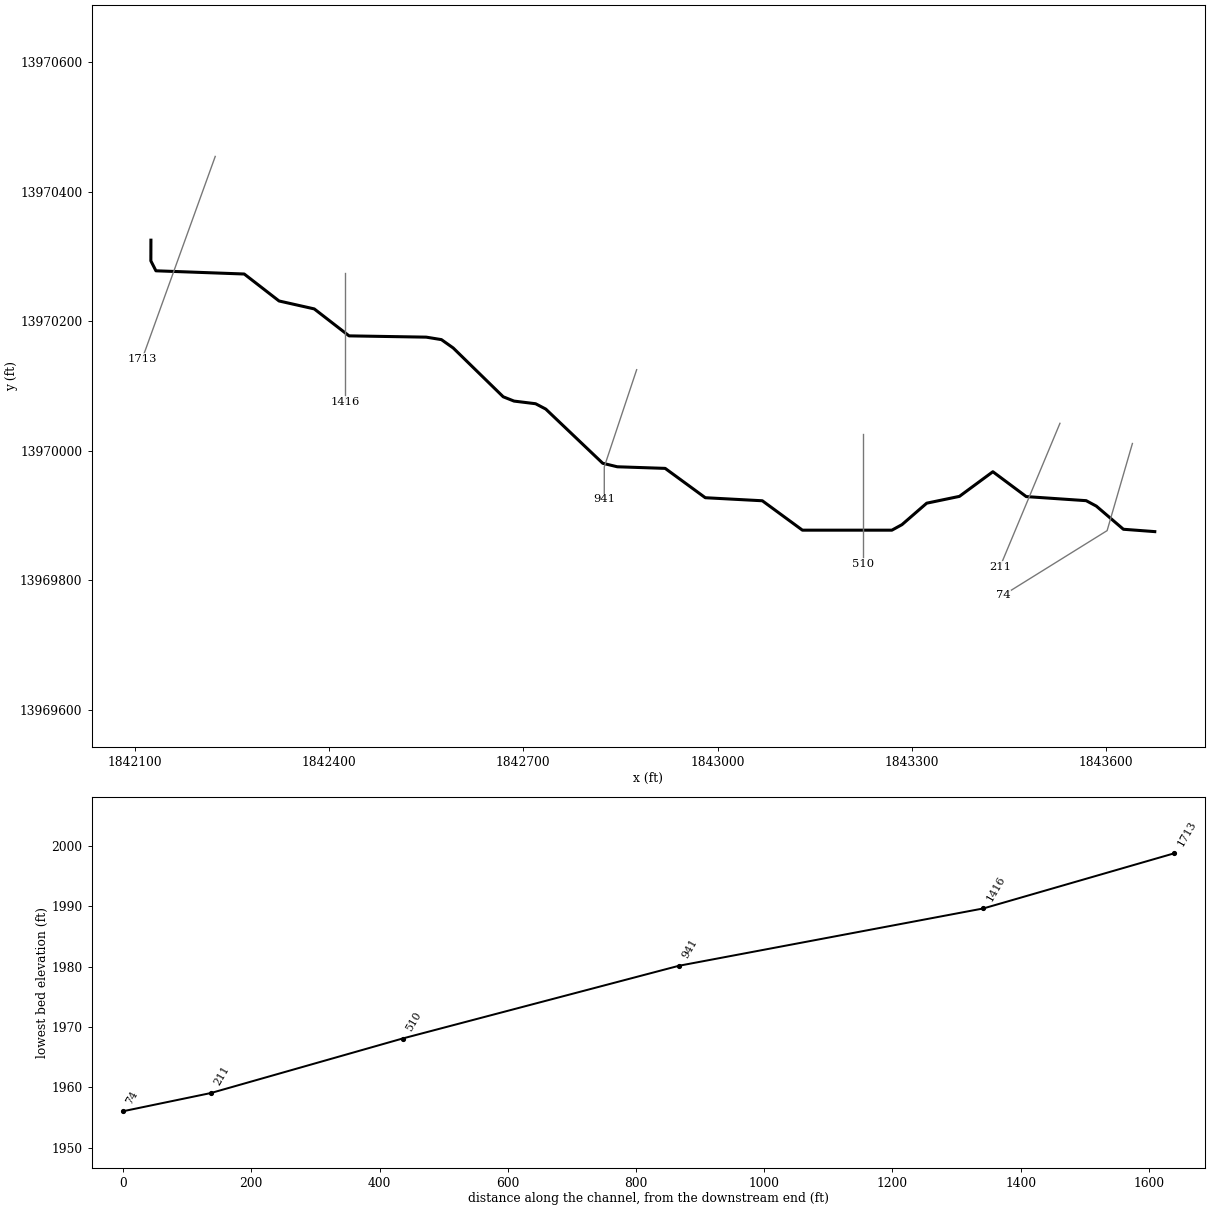
--- Stream0387.prj (project) ---

Proj Title=Stream0387 Base Level Engineering
Current Plan=p01
Default Exp/Contr=0.3,0.1
English Units
Geom File=g01
Flow File=f01
Plan File=p01
Y Axis Title=Elevation
X Axis Title(PF)=Main Channel Distance
X Axis Title(XS)=Station
BEGIN DESCRIPTION:
Stream0387
END DESCRIPTION:
DSS Export Rating Curves= 0
DSS Export Rating Curve Sorted= 0
DSS Export Volume Flow Curves= 0
DXF OffsetX= 0
DXF OffsetY= 0
DXF ScaleX= 1
DXF ScaleY= 10

--- Stream0387.p01 (plan) ---

Plan Title=Multiple Run
Short Identifier=Multiple
Geom File=g01
Flow File=f01
Subcritical Flow
K Sum by GR= 0
Std Step Tol= 0.01
Critical Tol= 0.01
Num of Std Step Trials= 20
Max Error Tol= 0.3
Flow Tol Ratio= 0.001
Split Flow NTrial= 30
Split Flow Tol= 0.02
Split Flow Ratio= 0.02
Log Output Level= 0
Friction Slope Method= 1
Unsteady Friction Slope Method= 2
Unsteady Bridges Friction Slope Method= 1
Parabolic Critical Depth
Global Vel Dist=  1 , 1 , 1
Global Log Level= 0
CheckData=True
Encroach Param= -1, 0, 0, 0
BEGIN DESCRIPTION:
Multiple Run
END DESCRIPTION:

--- Stream0387.f01 (steady flow) ---

Flow Title=Multiple
Program Version=4.10
Number of Profiles= 7
Profile Names=10-year,25-year,50-year,1pct_min,100-year,1pct_plu,500-year
River Rch & RM=Stream0387,Reach-1         ,1713
     907    1532    2120    1419    2832    5650    4989
Boundary for River Rch & Prof#=Stream0387,Reach-1         , 1
Up Type= 0
Dn Type= 3
Dn Slope=0.01
Boundary for River Rch & Prof#=Stream0387,Reach-1         , 2
Up Type= 0
Dn Type= 3
Dn Slope=0.01
Boundary for River Rch & Prof#=Stream0387,Reach-1         , 3
Up Type= 0
Dn Type= 3
Dn Slope=0.01
Boundary for River Rch & Prof#=Stream0387,Reach-1         , 4
Up Type= 0
Dn Type= 3
Dn Slope=0.01
Boundary for River Rch & Prof#=Stream0387,Reach-1         , 5
Up Type= 0
Dn Type= 3
Dn Slope=0.01
Boundary for River Rch & Prof#=Stream0387,Reach-1         , 6
Up Type= 0
Dn Type= 3
Dn Slope=0.01
Boundary for River Rch & Prof#=Stream0387,Reach-1         , 7
Up Type= 0
Dn Type= 3
Dn Slope=0.01
DSS Import GetInterval= 0
DSS Import GetPeak= 0
DSS Import FillOption= 0

--- Stream0387.g01 (geometry) ---

Geom Title=Existing Conditions

River Reach=Stream0387,Reach-1
Reach XY= 30
      1842125.00     13970325.00      1842124.90     13970293.05
      1842132.71     13970277.72      1842269.07     13970272.76
      1842322.82     13970231.12      1842377.18     13970218.88
      1842430.93     13970177.25      1842550.11     13970175.27
      1842573.53     13970171.45      1842591.75     13970158.54
      1842668.96     13970083.18      1842685.64     13970076.55
      1842718.95     13970072.46      1842734.67     13970064.20
      1842822.58     13969980.54      1842845.05     13969975.13
      1842919.02     13969972.64      1842980.97     13969927.35
      1843069.02     13969922.64      1843130.94     13969877.25
      1843269.07     13969877.23      1843284.67     13969885.79
      1843322.83     13969918.91      1843373.36     13969929.42
      1843424.99     13969967.47      1843476.50     13969929.09
      1843569.08     13969922.78      1843584.75     13969914.39
      1843626.51     13969878.64      1843675.00     13969875.00

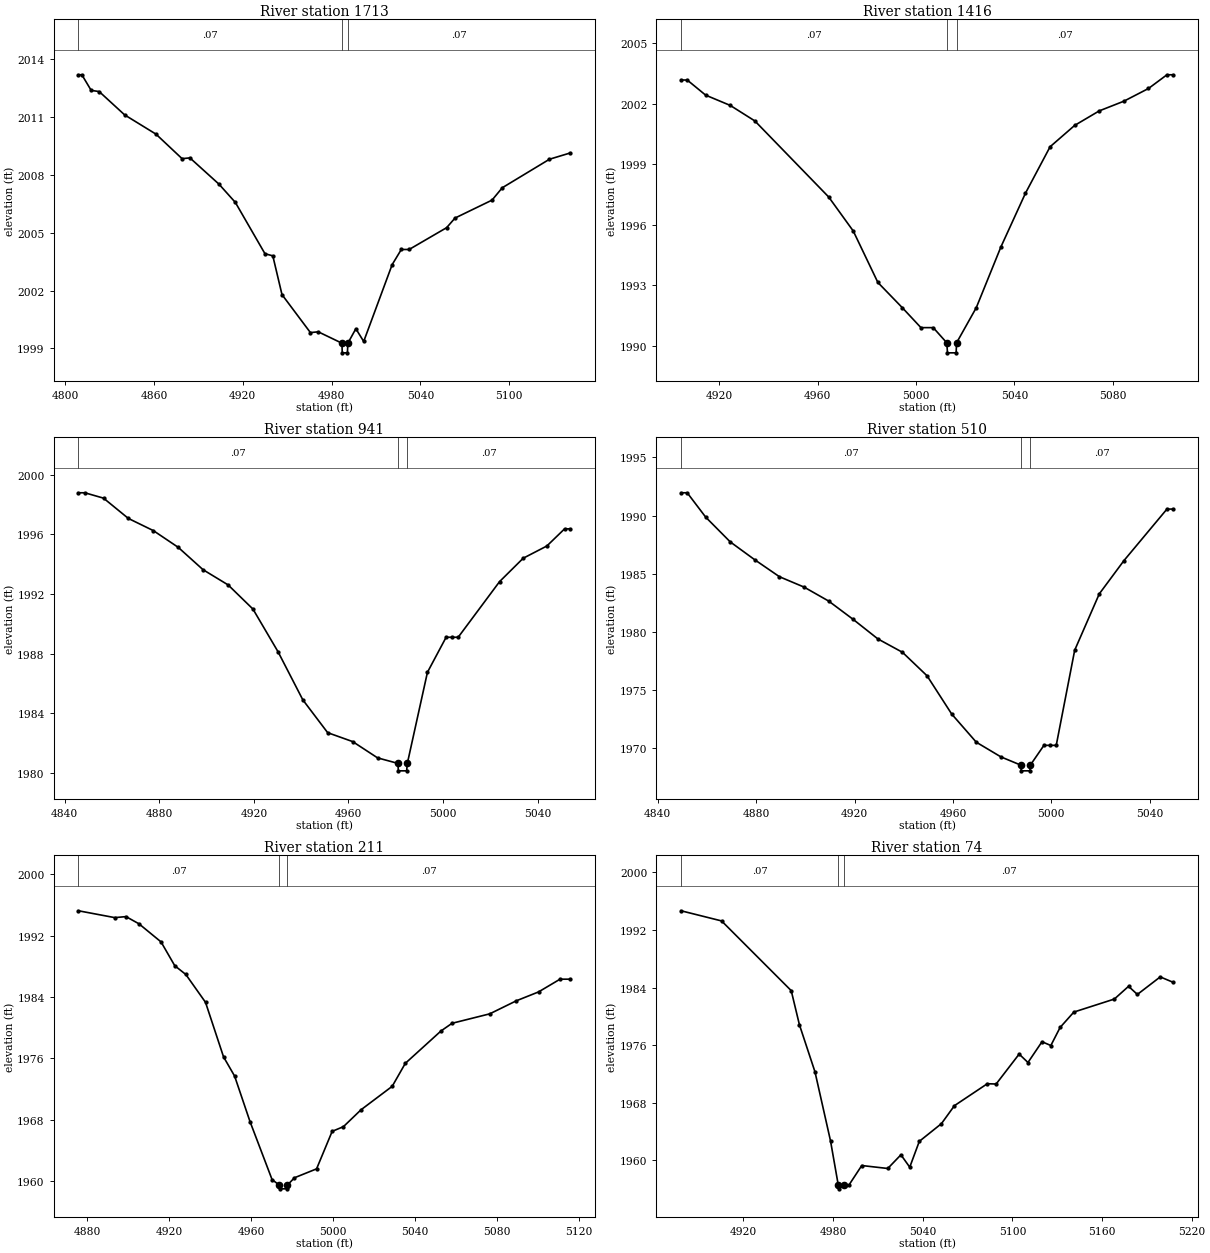
Type RM Length L Ch R = 1,1713,297,297,297
BEGIN DESCRIPTION:
Stream0387 4.0
END DESCRIPTION:
XS GIS Cut Line= 2
      1842224.31     13970454.31      1842111.49     13970141.64
#Sta/Elev= 30
  4809.0 2013.19  4811.3 2013.19  4817.6 2012.38  4823.0 2012.32  4840.2 2011.11
  4861.4 2010.11  4879.0 2008.84  4884.3 2008.88  4903.9 2007.52  4915.0 2006.57
  4935.0 2003.91  4940.3 2003.80  4946.5 2001.79  4965.7 1999.82  4971.0 1999.86
  4987.0 1999.27  4987.2 1998.77  4990.7 1998.77  4991.0 1999.27  4996.4 2000.02
  5001.7 1999.36  5020.9 2003.34  5027.1 2004.13  5032.4 2004.13  5057.7 2005.26
  5063.4 2005.76  5088.4 2006.69  5095.3 2007.33  5127.2 2008.81  5141.4 2009.14
#Mann=3,-1,0
  4809.0    0.07       0  4987.0    0.05       0  4991.0    0.07       0
Bank Sta=4987,4991
Exp/Cntr=0.3,0.1

Type RM Length L Ch R = 1,1416,475,475,475
BEGIN DESCRIPTION:
Stream0387 3.0
END DESCRIPTION:
XS GIS Cut Line= 3
      1842425.00     13970275.04      1842425.00     13970175.00
      1842425.00     13970075.04
#Sta/Elev= 25
  4904.5 2003.18  4907.0 2003.18  4914.5 2002.43  4924.5 2001.92  4934.5 2001.15
  4964.5 1997.38  4974.5 1995.69  4984.5 1993.14  4994.5 1991.88  5002.0 1990.90
  5007.0 1990.90  5012.5 1990.15  5012.8 1989.65  5016.3 1989.65  5016.5 1990.15
  5024.5 1991.89  5034.5 1994.90  5044.5 1997.57  5054.5 1999.87  5064.5 2000.93
  5074.5 2001.65  5084.5 2002.13  5094.5 2002.76  5102.0 2003.44  5104.5 2003.44
#Mann=3,-1,0
  4904.5    0.07       0  5012.5    0.05       0  5016.5    0.07       0
Bank Sta=5012.5,5016.5
Exp/Cntr=0.3,0.1

Type RM Length L Ch R = 1,941,431,431,431
BEGIN DESCRIPTION:
Stream0387 2.0
END DESCRIPTION:
XS GIS Cut Line= 3
      1842875.01     13970125.03      1842825.00     13969975.00
      1842825.00     13969925.05
#Sta/Elev= 27
  4845.8 1998.79  4848.5 1998.79  4856.4 1998.43  4866.9 1997.07  4877.5 1996.25
  4888.0 1995.13  4898.5 1993.63  4909.1 1992.61  4919.6 1990.99  4930.2 1988.13
  4940.7 1984.90  4951.2 1982.70  4961.8 1982.10  4972.3 1981.01  4980.9 1980.64
  4981.1 1980.14  4984.6 1980.14  4984.9 1980.64  4993.4 1986.75  5001.3 1989.10
  5003.9 1989.10  5006.4 1989.10  5023.9 1992.83  5033.9 1994.40  5043.9 1995.22
  5051.4 1996.37  5053.9 1996.37
#Mann=3,-1,0
  4845.8    0.07       0  4980.9    0.05       0  4984.9    0.07       0
Bank Sta=4980.9,4984.9
Exp/Cntr=0.3,0.1

Type RM Length L Ch R = 1,510,299,299,299
BEGIN DESCRIPTION:
Stream0387 1.0
END DESCRIPTION:
XS GIS Cut Line= 3
      1843225.00     13970025.02      1843225.00     13969875.00
      1843225.00     13969825.02
#Sta/Elev= 27
  4849.5 1991.96  4852.0 1991.96  4859.5 1989.87  4869.5 1987.74  4879.5 1986.20
  4889.5 1984.75  4899.5 1983.86  4909.5 1982.66  4919.5 1981.08  4929.5 1979.41
  4939.5 1978.26  4949.5 1976.24  4959.5 1972.96  4969.5 1970.54  4979.5 1969.28
  4987.5 1968.58  4987.8 1968.08  4991.3 1968.08  4991.5 1968.58  4997.0 1970.27
  4999.5 1970.27  5002.0 1970.27  5009.5 1978.44  5019.5 1983.28  5029.5 1986.13
  5047.0 1990.56  5049.5 1990.56
#Mann=3,-1,0
  4849.5    0.07       0  4987.5    0.05       0  4991.5    0.07       0
Bank Sta=4987.5,4991.5
Exp/Cntr=0.3,0.1

Type RM Length L Ch R = 1,211,137,137,137
BEGIN DESCRIPTION:
Stream0387 0.0
END DESCRIPTION:
XS GIS Cut Line= 2
      1843528.56     13970042.22      1843436.07     13969820.66
#Sta/Elev= 30
  4875.8 1995.22  4893.5 1994.33  4899.0 1994.46  4905.3 1993.53  4916.1 1991.17
  4922.8 1988.07  4928.2 1986.93  4937.8 1983.31  4946.6 1976.21  4952.0 1973.71
  4959.5 1967.80  4970.3 1960.23  4973.8 1959.54  4974.1 1959.04  4977.6 1959.04
  4977.8 1959.54  4981.2 1960.48  4992.0 1961.64  4999.6 1966.52  5005.1 1967.13
  5013.7 1969.33  5028.9 1972.38  5035.3 1975.37  5052.7 1979.58  5058.1 1980.58
  5076.5 1981.81  5089.5 1983.51  5100.3 1984.66  5110.8 1986.32  5115.9 1986.32
#Mann=3,-1,0
  4875.8    0.07       0  4973.8    0.05       0  4977.8    0.07       0
Bank Sta=4973.8,4977.8
Exp/Cntr=0.3,0.1

Type RM Length L Ch R = 1,74,0,0,0
BEGIN DESCRIPTION:
Stream0387 0.1
END DESCRIPTION:
XS GIS Cut Line= 3
      1843640.45     13970011.06      1843601.40     13969876.55
      1843440.78     13969776.70
#Sta/Elev= 30
  4878.3 1994.67  4905.4 1993.26  4952.0 1983.57  4957.5 1978.82  4967.9 1972.28
  4978.3 1962.68  4983.5 1956.52  4983.8 1956.02  4987.5 1956.52  4990.7 1956.57
  4999.2 1959.26  5016.6 1958.85  5025.4 1960.75  5031.3 1959.03  5037.7 1962.62
  5052.5 1965.08  5061.2 1967.58  5083.2 1970.63  5089.1 1970.59  5104.5 1974.75
  5110.4 1973.58  5119.8 1976.47  5125.7 1975.94  5131.9 1978.45  5141.1 1980.59
  5168.2 1982.40  5177.7 1984.17  5183.6 1983.04  5198.9 1985.48  5207.5 1984.73
#Mann=3,-1,0
  4878.3    0.07       0  4983.5    0.05       0  4987.5    0.07       0
Bank Sta=4983.5,4987.5
Exp/Cntr=0.3,0.1

Chan Stop Cuts=-1