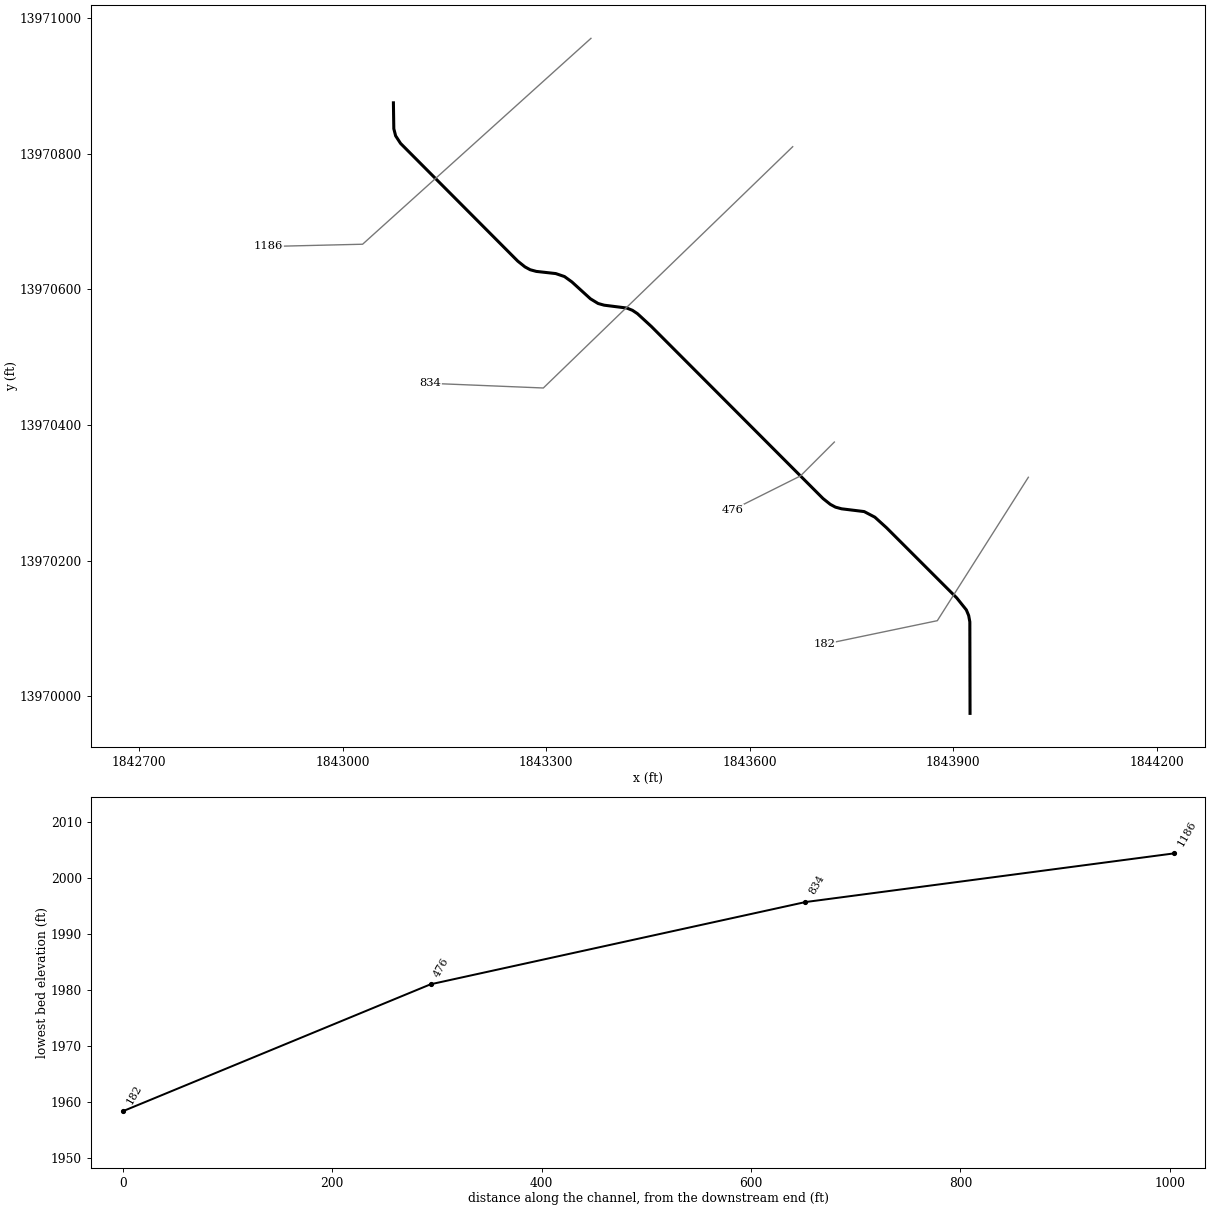
--- Stream0388.prj (project) ---

Proj Title=Stream0388 Base Level Engineering
Current Plan=p01
Default Exp/Contr=0.3,0.1
English Units
Geom File=g01
Flow File=f01
Plan File=p01
Y Axis Title=Elevation
X Axis Title(PF)=Main Channel Distance
X Axis Title(XS)=Station
BEGIN DESCRIPTION:
Stream0388
END DESCRIPTION:
DSS Export Rating Curves= 0
DSS Export Rating Curve Sorted= 0
DSS Export Volume Flow Curves= 0
DXF OffsetX= 0
DXF OffsetY= 0
DXF ScaleX= 1
DXF ScaleY= 10

--- Stream0388.p01 (plan) ---

Plan Title=Multiple Run
Short Identifier=Multiple
Geom File=g01
Flow File=f01
Subcritical Flow
K Sum by GR= 0
Std Step Tol= 0.01
Critical Tol= 0.01
Num of Std Step Trials= 20
Max Error Tol= 0.3
Flow Tol Ratio= 0.001
Split Flow NTrial= 30
Split Flow Tol= 0.02
Split Flow Ratio= 0.02
Log Output Level= 0
Friction Slope Method= 1
Unsteady Friction Slope Method= 2
Unsteady Bridges Friction Slope Method= 1
Parabolic Critical Depth
Global Vel Dist=  1 , 1 , 1
Global Log Level= 0
CheckData=True
Encroach Param= -1, 0, 0, 0
BEGIN DESCRIPTION:
Multiple Run
END DESCRIPTION:

--- Stream0388.f01 (steady flow) ---

Flow Title=Multiple
Number of Profiles=7
Profile Names=10-year,25-year,50-year,1pct_min,100-year,1pct_plu,500-year
River Rch & RM= Stream0388,Reach-1,1186
     362     577     768     497     991    1978    1626
Boundary for River Rch & Prof#=Stream0388,Reach-1,1
Up Type=0
Dn Type=3
Dn Slope=0.005
Boundary for River Rch & Prof#=Stream0388,Reach-1,2
Up Type=0
Dn Type=3
Dn Slope=0.005
Boundary for River Rch & Prof#=Stream0388,Reach-1,3
Up Type=0
Dn Type=3
Dn Slope=0.005
Boundary for River Rch & Prof#=Stream0388,Reach-1,4
Up Type=0
Dn Type=3
Dn Slope=0.005
Boundary for River Rch & Prof#=Stream0388,Reach-1,5
Up Type=0
Dn Type=3
Dn Slope=0.005
Boundary for River Rch & Prof#=Stream0388,Reach-1,6
Up Type=0
Dn Type=3
Dn Slope=0.005
Boundary for River Rch & Prof#=Stream0388,Reach-1,7
Up Type=0
Dn Type=3
Dn Slope=0.005

--- Stream0388.g01 (geometry) ---

Geom Title=Existing Conditions
Program Version=4.10

River Reach=Stream0388      ,Reach-1
Reach XY= 30
        1843075.       13970875.      1843075.59     13970836.84
      1843078.27     13970826.36      1843085.51     13970815.21
      1843258.32     13970641.64      1843268.94     13970633.14
      1843276.63     13970628.95      1843285.62      13970626.5
       1843314.3      13970623.3      1843327.19      13970618.9
      1843338.06     13970611.02      1843365.45      13970586.1
      1843376.74     13970579.19       1843385.7      13970576.7
      1843418.96      13970572.5       1843427.3     13970569.17
      1843434.68     13970564.24      1843455.16     13970545.39
      1843708.33     13970291.65      1843718.95     13970283.16
      1843726.65     13970278.98      1843735.64     13970276.55
      1843768.95     13970272.47      1843784.68     13970264.22
      1843801.82      13970248.7       1843905.4     13970145.17
      1843919.57     13970127.47      1843922.99     13970119.17
      1843924.69     13970109.87        1843925.       13969975.

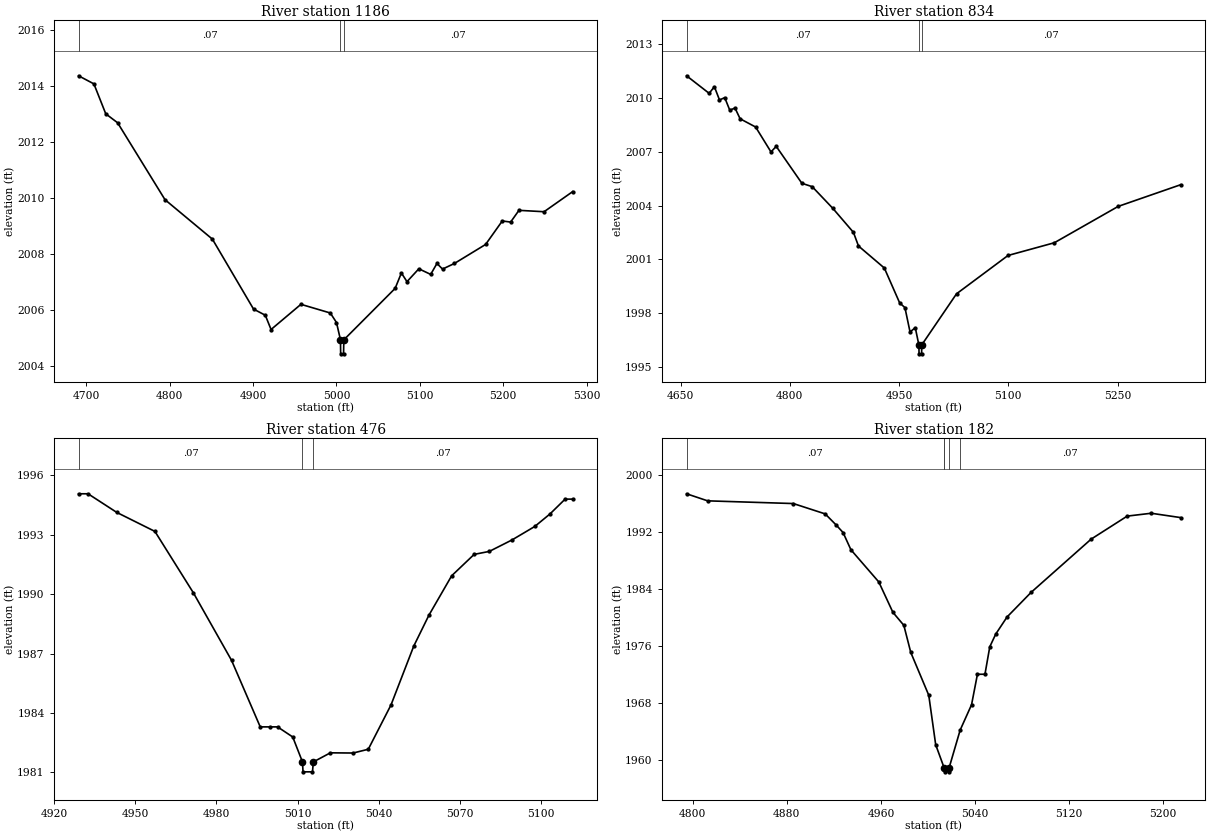
Type RM Length L Ch R = 1 ,1186    ,352,352,352
BEGIN DESCRIPTION:
Stream0388 3.0
END DESCRIPTION:
XS GIS Cut Line= 3
      1843366.21     13970970.06      1843029.59     13970666.56
      1842890.67     13970663.22
#Sta/Elev= 30
    4691 2014.37  4709.4 2014.08  4723.6 2013.01  4737.8 2012.69  4794.6 2009.94
  4851.4 2008.53  4900.7 2006.03  4914.8 2005.81  4921.7  2005.3  4957.5  2006.2
  4992.7 2005.89  5000.1 2005.55  5004.9 2004.93  5005.1 2004.43  5008.6 2004.43
  5008.9 2004.93  5070.4 2006.77  5077.9 2007.32  5084.6 2007.01  5098.8 2007.47
    5113 2007.27  5120.5 2007.66  5127.2 2007.46  5141.4 2007.66  5178.8 2008.34
  5198.8 2009.18  5208.8 2009.14  5218.8 2009.56  5248.9 2009.51  5283.2 2010.23
#Mann= 3 ,-1 , 0
    4691     .07       0  5004.9     .05       0  5008.9     .07       0
Bank Sta=5004.9,5008.9
XS Rating Curve= 0 ,0
Exp/Cntr=0.3,0.1

Type RM Length L Ch R = 1 ,834     ,358,358,358
BEGIN DESCRIPTION:
Stream0388 2.0
END DESCRIPTION:
XS GIS Cut Line= 3
      1843663.58     13970810.32        1843296.     13970454.64
      1843129.24     13970461.52
#Sta/Elev= 30
  4658.3 2011.25  4689.3 2010.27  4696.5 2010.64  4703.5  2009.9  4710.7 2010.03
  4717.6 2009.33  4724.8 2009.45  4731.8 2008.85  4753.1 2008.39  4774.2    2007
  4781.4 2007.31  4816.6 2005.25  4830.8 2005.06  4859.1 2003.85  4887.4 2002.51
  4894.3 2001.75  4929.8 2000.52  4950.9 1998.57  4958.1 1998.31  4965.1 1996.95
  4972.3 1997.19  4977.2 1996.23  4977.5 1995.73    4981 1995.73  4981.2 1996.23
  5028.9 1999.08  5099.6 2001.22  5163.2 2001.93  5250.9 2003.96  5336.7 2005.17
#Mann= 3 ,-1 , 0
  4658.3     .07       0  4977.2     .05       0  4981.2     .07       0
Bank Sta=4977.2,4981.2
XS Rating Curve= 0 ,0
Exp/Cntr=0.3,0.1

Type RM Length L Ch R = 1 ,476     ,294,294,294
BEGIN DESCRIPTION:
Stream0388 1.0
END DESCRIPTION:
XS GIS Cut Line= 3
      1843724.97     13970374.97        1843675.       13970325.
      1843574.98     13970274.99
#Sta/Elev= 28
  4929.1 1995.07  4932.6 1995.07  4943.2 1994.13  4957.3 1993.17  4971.5 1990.07
  4985.6 1986.66  4996.2  1983.3  4999.8  1983.3  5002.6  1983.3  5008.2 1982.79
  5011.8 1981.53    5012 1981.03  5015.5 1981.03  5015.8 1981.53  5022.1 1981.99
  5030.5 1981.98  5036.1 1982.17  5044.5 1984.41  5052.9 1987.38  5058.5 1988.94
  5066.9 1990.93  5075.2 1992.01  5080.8 1992.16  5089.2 1992.74  5097.6 1993.42
  5103.2 1994.05  5108.8  1994.8  5111.6  1994.8
#Mann= 3 ,-1 , 0
  4929.1     .07       0  5011.8     .05       0  5015.8     .07       0
Bank Sta=5011.8,5015.8
XS Rating Curve= 0 ,0
Exp/Cntr=0.3,0.1

Type RM Length L Ch R = 1 ,182     ,0,0,0
BEGIN DESCRIPTION:
Stream0388 0.0
END DESCRIPTION:
XS GIS Cut Line= 3
      1844010.94     13970323.03      1843876.76     13970111.64
      1843710.42     13970076.96
#Sta/Elev= 30
  4794.7 1997.31  4812.6 1996.32  4885.5 1995.94  4912.6 1994.49  4921.9 1992.94
  4927.8 1991.88  4934.5 1989.46  4958.2 1984.95  4970.2 1980.69  4979.5 1978.87
  4985.4 1975.07  5000.7 1969.07  5006.6 1962.13  5013.8 1958.88  5013.9 1958.83
  5014.2 1958.33  5017.7 1958.33  5017.9 1958.83  5027.4 1964.18  5037.1 1967.74
  5042.1 1972.01  5048.5 1972.01  5052.6 1975.86  5057.7 1977.65  5067.3 1980.04
  5087.7 1983.48  5138.8 1990.95  5169.5 1994.18  5189.9 1994.58    5215 1993.97
#Mann= 5 ,-1 , 0
  4794.7     .07       0  5013.8     .07       0  5013.9     .05       0
  5017.9     .07       0  5027.4     .07       0
Bank Sta=5013.9,5017.9
XS Rating Curve= 0 ,0
Exp/Cntr=0.3,0.1

Chan Stop Cuts=-1
Use User Specified Reach Order=0
Composite Channel Slope=5