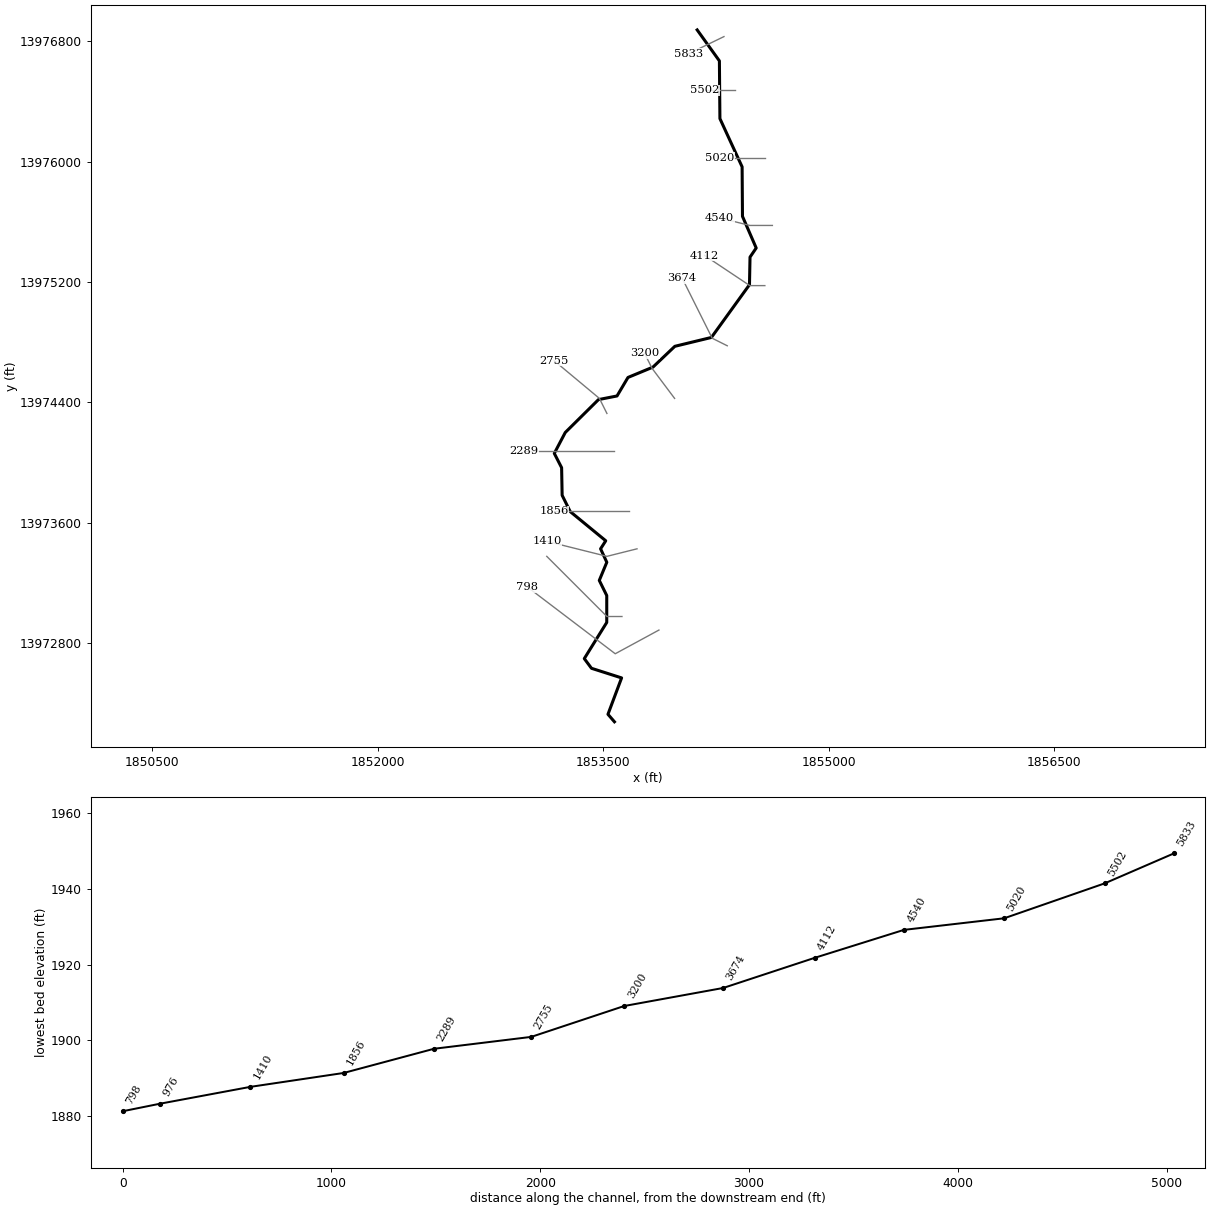
--- Stream0391.prj (project) ---

Proj Title=Stream0391 Base Level Engineering
Current Plan=p01
Default Exp/Contr=0.3,0.1
English Units
Geom File=g01
Flow File=f01
Plan File=p01
BEGIN DESCRIPTION:
Stream0391
END DESCRIPTION:

--- Stream0391.p01 (plan) ---

Plan Title=Multiple Run
Short Identifier=Multiple
Geom File=g01
Flow File=f01
Subcritical Flow
K Sum by GR= 0
Std Step Tol= 0.01
Critical Tol= 0.01
Num of Std Step Trials= 20
Max Error Tol= 0.3
Flow Tol Ratio= 0.001
Split Flow NTrial= 30
Split Flow Tol= 0.02
Split Flow Ratio= 0.02
Log Output Level= 0
Friction Slope Method= 1
Unsteady Friction Slope Method= 2
Unsteady Bridges Friction Slope Method= 1
Parabolic Critical Depth
Global Vel Dist=  1 , 1 , 1
Global Log Level= 0
CheckData=True
Encroach Param= -1, 0, 0, 0
BEGIN DESCRIPTION:
Multiple Run
END DESCRIPTION:

--- Stream0391.f01 (steady flow) ---

Flow Title=Multiple
Number of Profiles=7
Profile Names=10-year,25-year,50-year,1pct_min,100-year,1pct_plu,500-year
River Rch & RM= Stream0391,Reach-1,5833
    1828    3217    4576    3139    6263   12496   11606
Boundary for River Rch & Prof#=Stream0391,Reach-1,1
Up Type=0
Dn Type=3
Dn Slope=0.005
Boundary for River Rch & Prof#=Stream0391,Reach-1,2
Up Type=0
Dn Type=3
Dn Slope=0.005
Boundary for River Rch & Prof#=Stream0391,Reach-1,3
Up Type=0
Dn Type=3
Dn Slope=0.005
Boundary for River Rch & Prof#=Stream0391,Reach-1,4
Up Type=0
Dn Type=3
Dn Slope=0.005
Boundary for River Rch & Prof#=Stream0391,Reach-1,5
Up Type=0
Dn Type=3
Dn Slope=0.005
Boundary for River Rch & Prof#=Stream0391,Reach-1,6
Up Type=0
Dn Type=3
Dn Slope=0.005
Boundary for River Rch & Prof#=Stream0391,Reach-1,7
Up Type=0
Dn Type=3
Dn Slope=0.005

--- Stream0391.g01 (geometry) ---

Geom Title=Existing Conditions

River Reach=Stream0391,Reach-1
Reach XY= 30
      1854125.00     13976875.00      1854272.76     13976669.07
      1854276.22     13976285.50      1854423.80     13975964.50
      1854426.22     13975635.50      1854517.44     13975425.00
      1854476.38     13975364.56      1854472.76     13975180.93
      1854219.53     13974830.26      1853976.50     13974771.39
      1853831.06     13974633.14      1853665.00     13974564.37
      1853592.13     13974441.31      1853468.83     13974417.14
      1853248.01     13974198.47      1853175.08     13974059.61
      1853223.76     13973964.50      1853227.24     13973780.93
      1853280.83     13973672.70      1853517.11     13973478.58
      1853482.84     13973425.10      1853524.18     13973335.71
      1853474.23     13973214.95      1853523.78     13973114.50
      1853523.80     13972935.50      1853374.48     13972695.06
      1853422.38     13972630.73      1853622.51     13972566.85
      1853531.90     13972324.86      1853575.00     13972275.00

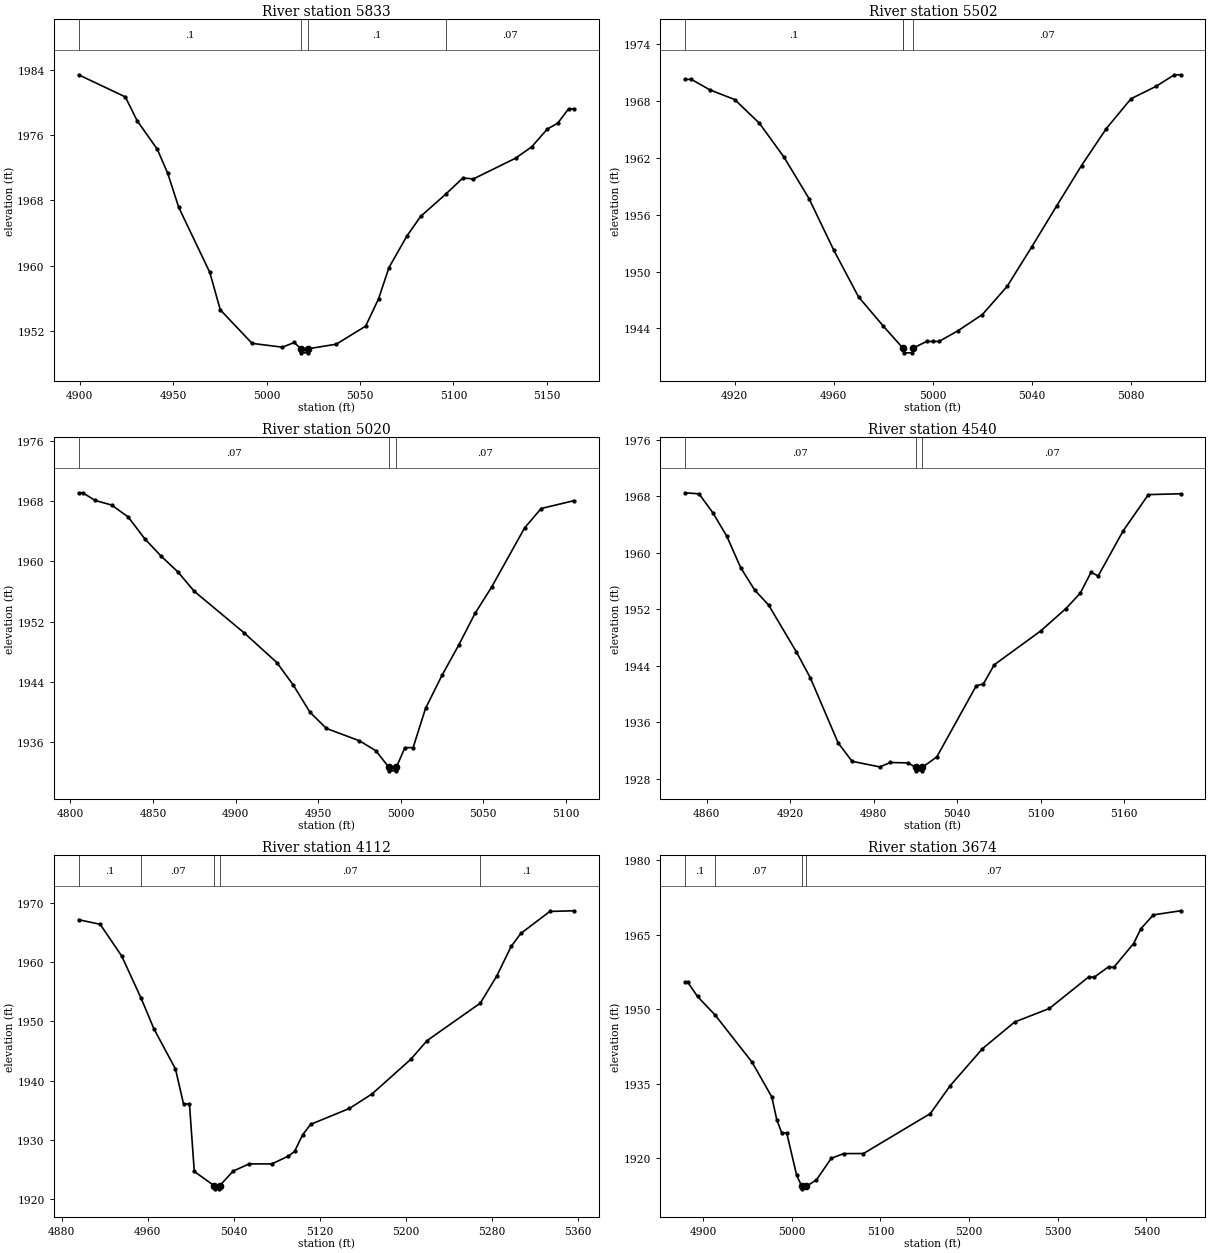
Type RM Length L Ch R = 1,5833,331,331,331
BEGIN DESCRIPTION:
Stream0391 12.0
END DESCRIPTION:
XS GIS Cut Line= 2
      1854303.21     13976830.60      1854064.55     13976714.95
#Sta/Elev= 30
  4899.4 1983.38  4924.4 1980.67  4930.7 1977.76  4941.5 1974.26  4947.0 1971.36
  4953.0 1967.13  4969.6 1959.18  4975.2 1954.60  4992.2 1950.49  5008.5 1950.02
  5014.8 1950.60  5018.3 1949.83  5018.6 1949.33  5022.1 1949.33  5022.3 1949.83
  5037.3 1950.39  5053.0 1952.60  5059.9 1955.94  5065.5 1959.78  5075.2 1963.68
  5082.5 1966.05  5095.8 1968.75  5105.1 1970.75  5110.6 1970.62  5133.2 1973.16
  5141.9 1974.56  5150.2 1976.73  5155.8 1977.45  5161.6 1979.21  5164.6 1979.21
#Mann=4,-1,0
  4899.4     0.1       0  5018.3    0.05       0  5022.3     0.1       0
  5095.8    0.07       0
Bank Sta=5018.3,5022.3
Exp/Cntr=0.3,0.1

Type RM Length L Ch R = 1,5502,482,482,482
BEGIN DESCRIPTION:
Stream0391 11.0
END DESCRIPTION:
XS GIS Cut Line= 3
      1854374.99     13976475.00      1854275.00     13976475.00
      1854174.99     13976475.00
#Sta/Elev= 29
  4900.0 1970.27  4902.5 1970.27  4910.0 1969.16  4920.0 1968.14  4930.0 1965.64
  4940.0 1962.03  4950.0 1957.70  4960.0 1952.26  4970.0 1947.33  4980.0 1944.25
  4987.8 1941.96  4987.9 1941.93  4988.2 1941.43  4991.7 1941.43  4992.0 1941.93
  4997.5 1942.63  5000.0 1942.63  5002.5 1942.63  5010.0 1943.74  5020.0 1945.47
  5030.0 1948.45  5040.0 1952.64  5050.0 1956.94  5060.0 1961.18  5070.0 1965.08
  5080.0 1968.23  5090.0 1969.52  5097.5 1970.75  5100.0 1970.75
#Mann=4,-1,0
  4900.0     0.1       0  4987.8    0.07       0  4987.9    0.05       0
  4992.0    0.07       0
Bank Sta=4987.9,4992
Exp/Cntr=0.3,0.1

Type RM Length L Ch R = 1,5020,480,480,480
BEGIN DESCRIPTION:
Stream0391 10.0
END DESCRIPTION:
XS GIS Cut Line= 3
      1854575.04     13976025.00      1854375.00     13976025.00
      1854275.04     13976025.00
#Sta/Elev= 30
  4805.0 1969.12  4807.5 1969.12  4815.0 1968.10  4825.0 1967.49  4835.0 1965.91
  4845.0 1963.02  4855.0 1960.69  4865.0 1958.64  4875.0 1956.04  4905.0 1950.56
  4925.0 1946.58  4935.0 1943.57  4945.0 1940.00  4955.0 1937.83  4975.0 1936.19
  4985.0 1934.86  4992.7 1932.70  4993.0 1932.20  4997.1 1932.20  4997.4 1932.70
  5002.5 1935.28  5007.5 1935.28  5015.0 1940.48  5025.0 1944.89  5035.0 1948.86
  5045.0 1953.11  5055.0 1956.59  5075.0 1964.46  5085.0 1967.03  5105.0 1968.08
#Mann=3,-1,0
  4805.0    0.07       0  4992.7    0.05       0  4997.4    0.07       0
Bank Sta=4992.7,4997.4
Exp/Cntr=0.3,0.1

Type RM Length L Ch R = 1,4540,428,428,428
BEGIN DESCRIPTION:
Stream0391 9.0
END DESCRIPTION:
XS GIS Cut Line= 3
      1854625.02     13975575.00      1854475.00     13975575.00
      1854274.97     13975625.01
#Sta/Elev= 30
  4844.5 1968.47  4854.5 1968.32  4864.5 1965.63  4874.5 1962.32  4884.5 1957.86
  4894.5 1954.72  4904.5 1952.60  4924.5 1945.96  4934.5 1942.30  4954.5 1933.10
  4964.5 1930.49  4984.5 1929.69  4992.0 1930.32  5004.8 1930.26  5010.2 1929.64
  5010.5 1929.14  5014.6 1929.14  5015.0 1929.64  5025.4 1931.10  5053.8 1941.18
  5058.9 1941.43  5066.7 1944.14  5100.2 1948.94  5118.2 1952.09  5128.5 1954.25
  5136.3 1957.23  5141.4 1956.70  5159.4 1963.09  5177.5 1968.21  5200.7 1968.33
#Mann=3,-1,0
  4844.5    0.07       0  5010.2    0.05       0  5015.0    0.07       0
Bank Sta=5010.2,5015
Exp/Cntr=0.3,0.1

Type RM Length L Ch R = 1,4112,438,438,438
BEGIN DESCRIPTION:
Stream0391 8.0
END DESCRIPTION:
XS GIS Cut Line= 3
      1854575.01     13975175.00      1854475.00     13975175.00
      1854174.97     13975375.02
#Sta/Elev= 30
  4895.8 1967.18  4915.8 1966.41  4935.8 1961.06  4953.9 1953.92  4965.8 1948.75
  4985.8 1941.99  4993.3 1936.08  4998.8 1936.08  5003.3 1924.68  5022.0 1922.25
  5022.3 1921.75  5026.4 1921.75  5026.8 1922.25  5039.4 1924.75  5054.4 1925.96
  5075.4 1925.96  5090.5 1927.25  5096.5 1928.06  5104.0 1930.87  5111.5 1932.64
  5147.5 1935.32  5168.6 1937.78  5204.6 1943.63  5219.7 1946.78  5269.1 1953.09
  5284.3 1957.63  5297.8 1962.66  5306.8 1964.86  5333.8 1968.58  5356.4 1968.69
#Mann=5,-1,0
  4895.8     0.1       0  4953.9    0.07       0  5022.0    0.05       0
  5026.8    0.07       0  5269.1     0.1       0
Bank Sta=5022,5026.8
Exp/Cntr=0.3,0.1

Type RM Length L Ch R = 1,3674,474,474,474
BEGIN DESCRIPTION:
Stream0391 7.0
END DESCRIPTION:
XS GIS Cut Line= 3
      1854324.99     13974775.01      1854225.00     13974825.00
      1854025.00     13975225.00
#Sta/Elev= 30
  4879.7 1955.47  4882.5 1955.47  4893.7 1952.55  4913.6 1948.80  4955.2 1939.33
  4977.5 1932.31  4983.1 1927.75  4988.7 1925.08  4994.3 1925.08  5005.5 1916.56
  5011.3 1914.30  5011.7 1913.80  5016.4 1914.30  5027.8 1915.59  5044.6 1919.95
  5058.6 1920.90  5080.9 1920.91  5156.4 1928.97  5178.8 1934.59  5215.1 1942.02
  5251.4 1947.40  5290.6 1950.13  5335.3 1956.53  5340.9 1956.39  5357.6 1958.55
  5363.2 1958.39  5385.6 1963.21  5394.0 1966.23  5408.0 1968.99  5438.7 1969.81
#Mann=4,-1,0
  4879.7     0.1       0  4913.6    0.07       0  5011.3    0.05       0
  5016.4    0.07       0
Bank Sta=5011.3,5016.4
Exp/Cntr=0.3,0.1

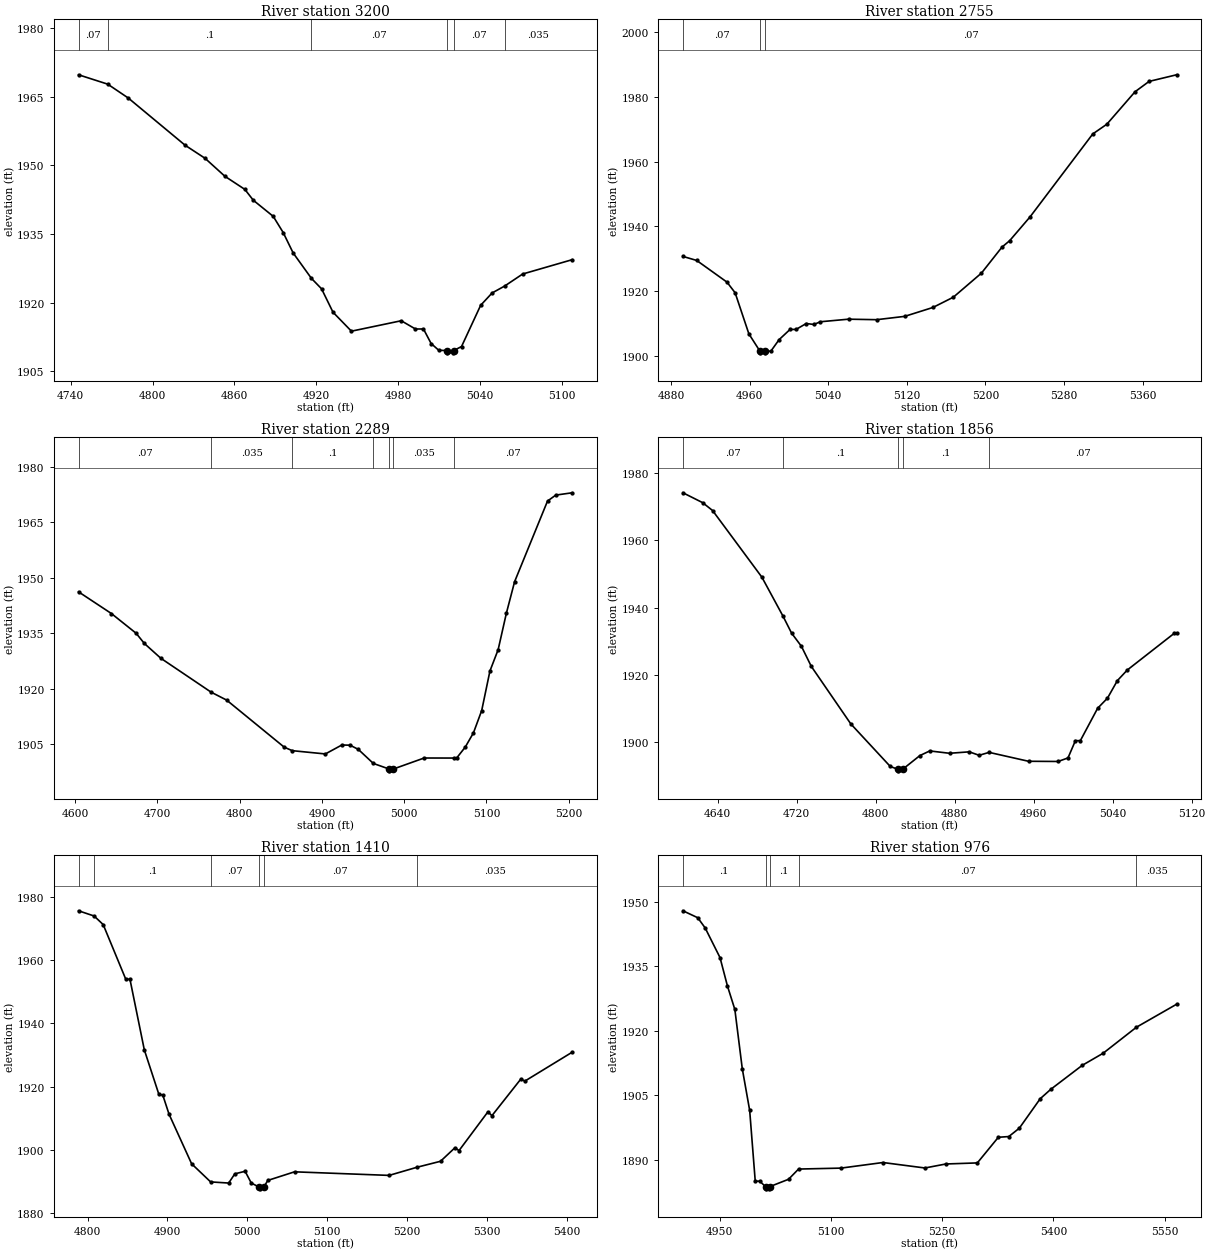
Type RM Length L Ch R = 1,3200,445,445,445
BEGIN DESCRIPTION:
Stream0391 6.0
END DESCRIPTION:
XS GIS Cut Line= 3
      1853975.00     13974425.00      1853825.00     13974625.00
      1853775.00     13974725.00
#Sta/Elev= 30
  4745.7 1969.78  4767.1 1967.73  4782.2 1964.69  4823.8 1954.39  4838.4 1951.54
  4853.0 1947.60  4867.6 1944.74  4873.8 1942.37  4888.4 1938.85  4895.7 1935.31
  4903.0 1930.85  4916.4 1925.30  4923.8 1923.03  4932.2 1917.91  4945.7 1913.77
  4982.2 1916.05  4992.6 1914.25  4998.5 1914.25  5004.1 1911.08  5009.7 1909.60
  5015.5 1909.54  5015.9 1909.04  5020.3 1909.04  5020.7 1909.54  5026.4 1910.42
  5040.4 1919.42  5048.8 1922.12  5058.0 1923.63  5071.2 1926.26  5107.5 1929.39
#Mann=6,-1,0
  4745.7    0.07       0  4767.1     0.1       0  4916.4    0.07       0
  5015.5    0.05       0  5020.7    0.07       0  5058.0   0.035       0
Bank Sta=5015.5,5020.7
Exp/Cntr=0.3,0.1

Type RM Length L Ch R = 1,2755,466,466,466
BEGIN DESCRIPTION:
Stream0391 5.0
END DESCRIPTION:
XS GIS Cut Line= 3
      1853525.02     13974324.96      1853475.00     13974425.00
      1853174.97     13974675.03
#Sta/Elev= 30
  4892.1 1930.71  4906.1 1929.46  4936.9 1922.76  4945.2 1919.47  4959.2 1906.76
  4970.5 1901.39  4971.0 1900.89  4975.4 1900.89  4975.8 1901.39  4981.6 1901.42
  4990.0 1904.98  5001.1 1908.13  5007.2 1908.13  5017.6 1909.96  5025.4 1909.66
  5031.9 1910.50  5060.6 1911.30  5089.2 1911.14  5117.8 1912.17  5146.5 1914.92
  5167.3 1918.10  5195.9 1925.55  5216.8 1933.59  5224.6 1935.57  5245.4 1942.95
  5309.2 1968.59  5323.5 1971.59  5352.2 1981.63  5366.5 1984.83  5394.5 1986.88
#Mann=3,-1,0
  4892.1    0.07       0  4970.5    0.05       0  4975.8    0.07       0
Bank Sta=4970.5,4975.8
Exp/Cntr=0.3,0.1

Type RM Length L Ch R = 1,2289,433,433,433
BEGIN DESCRIPTION:
Stream0391 4.0
END DESCRIPTION:
XS GIS Cut Line= 3
      1853575.02     13974075.00      1853175.00     13974075.00
      1852975.02     13974075.00
#Sta/Elev= 30
  4604.2 1946.18  4644.2 1940.30  4674.2 1934.97  4684.2 1932.21  4704.2 1928.21
  4765.3 1919.04  4784.2 1916.89  4854.2 1904.15  4863.9 1903.21  4904.2 1902.32
  4924.2 1904.74  4934.2 1904.69  4944.2 1903.56  4962.5 1899.75  4981.6 1898.25
  4982.0 1897.75  4986.9 1898.25  5024.2 1901.22  5061.1 1901.21  5064.2 1901.34
  5074.2 1904.17  5084.2 1908.04  5094.2 1914.06  5104.2 1924.75  5114.2 1930.54
  5124.2 1940.40  5134.2 1948.93  5174.2 1970.74  5184.2 1972.35  5204.2 1972.98
#Mann=7,-1,0
  4604.2    0.07       0  4765.3   0.035       0  4863.9     0.1       0
  4962.5   0.035       0  4981.6   0.035       0  4986.9   0.035       0
  5061.1    0.07       0
Bank Sta=4981.6,4986.9
Exp/Cntr=0.3,0.1

Type RM Length L Ch R = 1,1856,446,446,446
BEGIN DESCRIPTION:
Stream0391 3.0
END DESCRIPTION:
XS GIS Cut Line= 3
      1853675.03     13973675.00      1853275.00     13973675.00
      1853175.03     13973675.00
#Sta/Elev= 30
  4604.7 1974.19  4624.7 1971.24  4634.7 1968.91  4684.7 1949.03  4706.1 1937.41
  4714.7 1932.40  4724.7 1928.46  4734.7 1922.48  4774.7 1905.35  4814.7 1892.66
  4822.1 1891.86  4822.5 1891.36  4827.4 1891.86  4844.7 1895.91  4854.7 1897.29
  4874.7 1896.59  4894.7 1897.02  4904.7 1895.99  4914.8 1896.86  4954.7 1894.21
  4984.7 1894.15  4994.7 1895.21  5002.2 1900.35  5007.2 1900.35  5024.7 1909.99
  5034.7 1913.02  5044.7 1918.23  5054.7 1921.38  5102.2 1932.30  5104.7 1932.30
#Mann=5,-1,0
  4604.7    0.07       0  4706.1     0.1       0  4822.1    0.05       0
  4827.4     0.1       0  4914.8    0.07       0
Bank Sta=4822.1,4827.4
Exp/Cntr=0.3,0.1

Type RM Length L Ch R = 1,1410,434,434,434
BEGIN DESCRIPTION:
Stream0391 2.0
END DESCRIPTION:
XS GIS Cut Line= 3
      1853724.99     13973425.00      1853525.00     13973375.00
      1853124.95     13973475.01
#Sta/Elev= 30
  4788.6 1975.60  4808.1 1973.95  4819.5 1971.23  4847.9 1953.89  4853.0 1953.98
  4871.0 1931.65  4889.1 1917.69  4894.2 1917.30  4902.0 1911.29  4930.3 1895.61
  4954.1 1889.89  4976.7 1889.53  4984.4 1892.44  4997.3 1893.25  5005.0 1889.54
  5015.2 1888.20  5015.7 1887.70  5020.6 1888.20  5025.7 1890.36  5059.2 1893.08
  5177.7 1891.95  5212.6 1894.52  5242.1 1896.41  5260.2 1900.69  5265.3 1899.79
  5301.4 1912.01  5306.6 1910.85  5342.6 1922.36  5347.8 1921.76  5407.1 1930.90
#Mann=6,-1,0
  4788.6    0.07       0  4808.1     0.1       0  4954.1    0.07       0
  5015.2    0.05       0  5020.6    0.07       0  5212.6   0.035       0
Bank Sta=5015.2,5020.6
Exp/Cntr=0.3,0.1

Type RM Length L Ch R = 1,976,178,178,178
BEGIN DESCRIPTION:
Stream0391 1.0
END DESCRIPTION:
XS GIS Cut Line= 3
      1853625.01     13972975.00      1853525.00     13972975.00
      1853125.00     13973375.00
#Sta/Elev= 30
  4900.4 1947.90  4920.4 1946.28  4930.4 1943.90  4950.4 1937.01  4960.4 1930.42
  4970.4 1924.95  4980.4 1911.20  4990.4 1901.47  4997.9 1885.02  5003.9 1885.02
  5011.9 1883.74  5012.3 1883.24  5016.8 1883.24  5017.3 1883.74  5042.8 1885.46
  5056.3 1887.84  5113.5 1888.06  5170.1 1889.36  5226.7 1888.09  5255.0 1889.02
  5297.4 1889.27  5325.7 1895.23  5339.8 1895.40  5354.0 1897.34  5382.2 1904.20
  5396.4 1906.38  5438.8 1911.95  5467.1 1914.78  5511.9 1920.82  5566.1 1926.17
#Mann=5,-1,0
  4900.4     0.1       0  5011.9    0.05       0  5017.3     0.1       0
  5056.3    0.07       0  5511.9   0.035       0
Bank Sta=5011.9,5017.3
Exp/Cntr=0.3,0.1

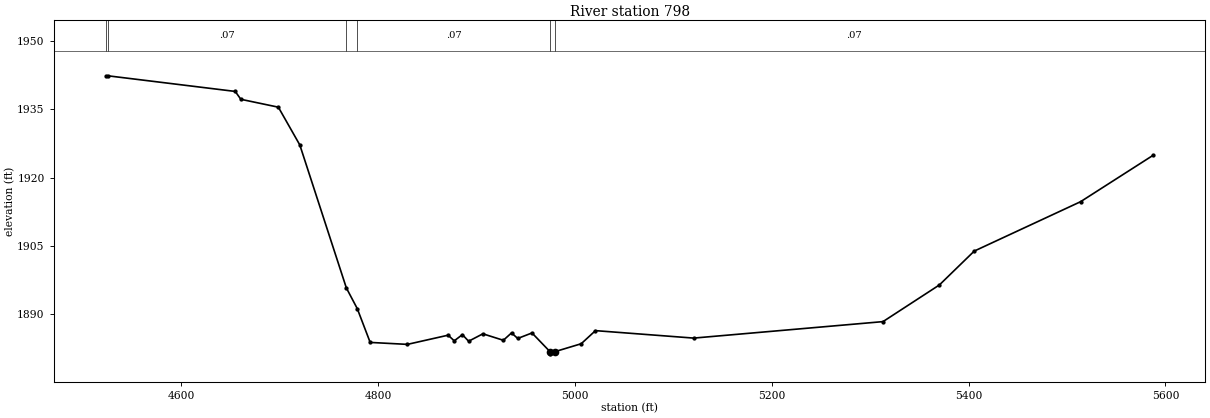
Type RM Length L Ch R = 1,798,0,0,0
BEGIN DESCRIPTION:
Stream0391 0.0
END DESCRIPTION:
XS GIS Cut Line= 3
      1853870.79     13972884.94      1853580.27     13972727.39
      1852996.53     13973170.90
#Sta/Elev= 30
  4523.9 1942.29  4525.4 1942.37  4655.0 1938.93  4660.7 1937.20  4698.8 1935.47
  4720.6 1927.17  4767.9 1895.74  4779.0 1891.19  4792.1 1883.77  4829.9 1883.34
  4871.3 1885.36  4877.5 1884.12  4885.8 1885.48  4892.1 1884.03  4906.6 1885.66
  4927.4 1884.24  4935.7 1885.86  4942.0 1884.64  4956.5 1885.85  4974.7 1881.76
  4975.1 1881.26  4980.1 1881.76  5006.5 1883.48  5021.0 1886.36  5120.8 1884.72
  5313.1 1888.34  5370.4 1896.40  5405.8 1903.84  5513.8 1914.69  5587.5 1924.89
#Mann=6,-1,0
  4523.9   0.035       0  4525.4    0.07       0  4767.9     0.1       0
  4779.0    0.07       0  4974.7    0.05       0  4980.1    0.07       0
Bank Sta=4974.7,4980.1
Exp/Cntr=0.3,0.1

Chan Stop Cuts=-1