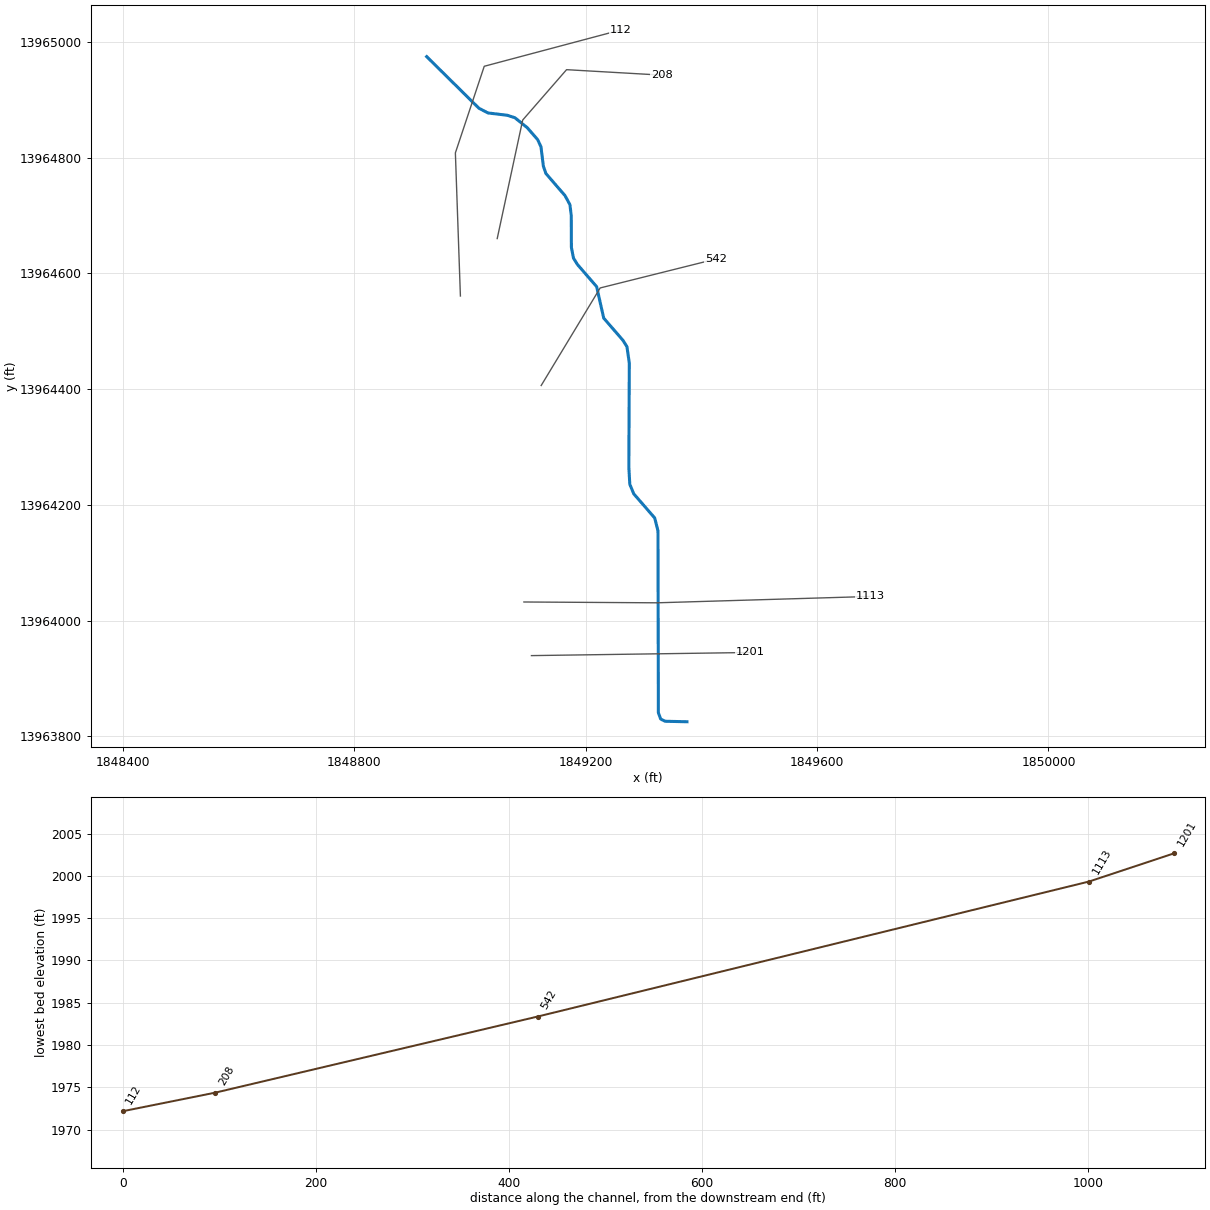
--- Stream0393.prj (project) ---

Proj Title=Stream0393 Base Level Engineering
Current Plan=p01
Default Exp/Contr=0.3,0.1
English Units
Geom File=g01
Flow File=f01
Plan File=p01
BEGIN DESCRIPTION:
Stream0393
END DESCRIPTION:

--- Stream0393.p01 (plan) ---

Plan Title=Multiple Run
Short Identifier=Multiple
Geom File=g01
Flow File=f01
Subcritical Flow
K Sum by GR= 0
Std Step Tol= 0.01
Critical Tol= 0.01
Num of Std Step Trials= 20
Max Error Tol= 0.3
Flow Tol Ratio= 0.001
Split Flow NTrial= 30
Split Flow Tol= 0.02
Split Flow Ratio= 0.02
Log Output Level= 0
Friction Slope Method= 1
Unsteady Friction Slope Method= 2
Unsteady Bridges Friction Slope Method= 1
Parabolic Critical Depth
Global Vel Dist=  1 , 1 , 1
Global Log Level= 0
CheckData=True
Encroach Param= -1, 0, 0, 0
BEGIN DESCRIPTION:
Multiple Run
END DESCRIPTION:

--- Stream0393.f01 (steady flow) ---

Flow Title=Multiple
Number of Profiles=7
Profile Names=10-year,25-year,50-year,1pct_min,100-year,1pct_plu,500-year
River Rch & RM= Stream0393,Reach-1,1201
     394     633     848     552    1101    2197    1827
Boundary for River Rch & Prof#=Stream0393,Reach-1,1
Up Type=0
Dn Type=3
Dn Slope=0.005
Boundary for River Rch & Prof#=Stream0393,Reach-1,2
Up Type=0
Dn Type=3
Dn Slope=0.005
Boundary for River Rch & Prof#=Stream0393,Reach-1,3
Up Type=0
Dn Type=3
Dn Slope=0.005
Boundary for River Rch & Prof#=Stream0393,Reach-1,4
Up Type=0
Dn Type=3
Dn Slope=0.005
Boundary for River Rch & Prof#=Stream0393,Reach-1,5
Up Type=0
Dn Type=3
Dn Slope=0.005
Boundary for River Rch & Prof#=Stream0393,Reach-1,6
Up Type=0
Dn Type=3
Dn Slope=0.005
Boundary for River Rch & Prof#=Stream0393,Reach-1,7
Up Type=0
Dn Type=3
Dn Slope=0.005

--- Stream0393.g01 (geometry) ---

Geom Title=Existing Conditions

River Reach=Stream0393,Reach-1
Reach XY= 30
      1849375.00     13963825.00      1849337.43     13963825.83
      1849329.63     13963829.63      1849325.61     13963840.61
      1849324.93     13964154.97      1849319.25     13964177.33
      1849283.14     13964218.94      1849276.22     13964235.50
      1849274.55     13964264.81      1849275.36     13964445.15
      1849271.25     13964473.45      1849264.20     13964484.67
      1849231.12     13964522.82      1849218.89     13964577.18
      1849185.84     13964615.35      1849178.83     13964626.58
      1849175.23     13964645.10      1849175.01     13964700.00
      1849172.67     13964719.04      1849164.17     13964734.66
      1849131.15     13964772.85      1849126.74     13964785.76
      1849122.58     13964819.15      1849116.98     13964831.34
      1849098.84     13964852.14      1849077.54     13964869.26
      1849064.52     13964873.53      1849031.08     13964877.54
      1849015.31     13964885.72      1848925.00     13964975.00

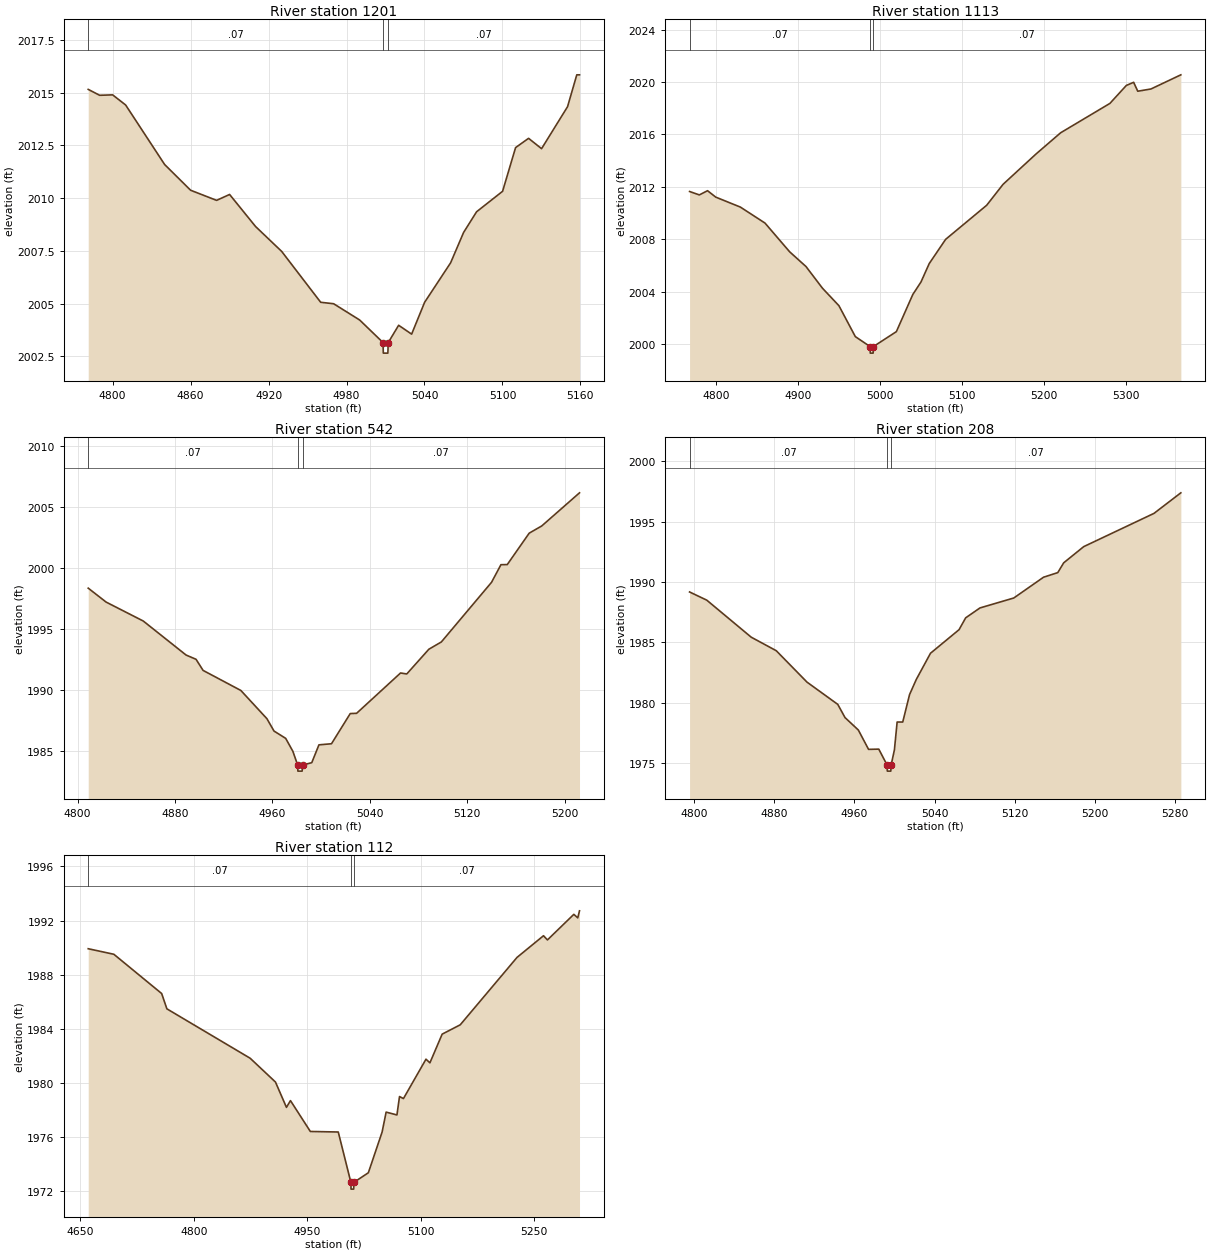
Type RM Length L Ch R = 1,1201,88,88,88
BEGIN DESCRIPTION:
Stream0393 3.0
END DESCRIPTION:
XS GIS Cut Line= 2
      1849106.16     13963939.35      1849484.22     13963944.76
#Sta/Elev= 30
  4781.2 2015.15  4790.0 2014.87  4800.0 2014.89  4810.0 2014.41  4840.0 2011.59
  4860.0 2010.37  4880.0 2009.89  4890.0 2010.17  4910.0 2008.65  4930.1 2007.47
  4960.1 2005.06  4970.1 2004.99  4990.1 2004.22  5008.1 2003.15  5008.3 2002.65
  5011.8 2002.65  5012.1 2003.15  5020.1 2003.97  5030.1 2003.55  5040.1 2005.06
  5060.1 2006.93  5070.1 2008.37  5080.1 2009.35  5100.1 2010.32  5110.1 2012.39
  5120.1 2012.83  5130.1 2012.34  5150.1 2014.33  5157.2 2015.84  5159.3 2015.84
#Mann=3,-1,0
  4781.2    0.07       0  5008.1    0.05       0  5012.1    0.07       0
Bank Sta=5008.1,5012.1
Exp/Cntr=0.3,0.1

Type RM Length L Ch R = 1,1113,571,571,571
BEGIN DESCRIPTION:
Stream0393 2.0
END DESCRIPTION:
XS GIS Cut Line= 3
      1849093.13     13964032.06      1849323.34     13964030.64
      1849691.36     13964041.60
#Sta/Elev= 30
  4768.1 2011.65  4780.0 2011.39  4790.0 2011.71  4800.0 2011.22  4830.0 2010.46
  4860.0 2009.24  4890.0 2007.05  4910.0 2005.92  4930.0 2004.27  4950.0 2002.94
  4970.0 2000.58  4988.0 1999.82  4988.2 1999.32  4991.7 1999.32  4992.0 1999.82
  5020.0 2000.96  5040.0 2003.79  5050.0 2004.75  5060.0 2006.15  5080.0 2008.00
  5130.0 2010.60  5150.0 2012.20  5190.1 2014.51  5220.1 2016.13  5280.1 2018.37
  5300.1 2019.74  5309.0 2019.98  5314.0 2019.30  5330.1 2019.47  5366.5 2020.55
#Mann=3,-1,0
  4768.1    0.07       0  4988.0    0.05       0  4992.0    0.07       0
Bank Sta=4988,4992
Exp/Cntr=0.3,0.1

Type RM Length L Ch R = 1,542,334,334,334
BEGIN DESCRIPTION:
Stream0393 1.0
END DESCRIPTION:
XS GIS Cut Line= 3
      1849123.01     13964406.33      1849225.00     13964575.00
      1849425.03     13964625.01
#Sta/Elev= 30
  4808.8 1998.33  4823.5 1997.19  4854.0 1995.64  4889.1 1992.86  4897.3 1992.51
  4903.1 1991.60  4934.1 1989.96  4955.5 1987.65  4961.3 1986.64  4970.9 1986.04
  4976.8 1984.98  4980.7 1983.86  4980.9 1983.36  4984.4 1983.36  4984.7 1983.86
  4992.3 1984.05  4998.2 1985.51  5008.5 1985.60  5023.9 1988.07  5029.1 1988.09
  5065.2 1991.39  5070.3 1991.31  5088.4 1993.33  5098.7 1993.93  5139.9 1998.81
  5147.6 2000.25  5152.8 2000.26  5170.8 2002.83  5181.1 2003.42  5212.1 2006.13
#Mann=3,-1,0
  4808.8    0.07       0  4980.7    0.05       0  4984.7    0.07       0
Bank Sta=4980.7,4984.7
Exp/Cntr=0.3,0.1

Type RM Length L Ch R = 1,208,96,96,96
BEGIN DESCRIPTION:
Stream0393 0.0
END DESCRIPTION:
XS GIS Cut Line= 4
      1849046.98     13964660.38      1849091.03     13964865.28
      1849166.88     13964952.38      1849331.74     13964942.92
#Sta/Elev= 30
  4795.5 1989.18  4812.7 1988.50  4857.0 1985.44  4882.0 1984.32  4912.7 1981.72
  4943.4 1979.88  4950.6 1978.79  4963.9 1977.76  4974.1 1976.16  4984.3 1976.18
  4992.6 1974.86  4992.8 1974.36  4996.3 1974.36  4996.6 1974.86  4999.9 1976.12
  5002.6 1978.42  5008.2 1978.42  5015.0 1980.69  5021.7 1981.94  5035.9 1984.11
  5064.4 1986.06  5071.0 1987.04  5085.3 1987.86  5119.0 1988.68  5148.7 1990.40
  5162.9 1990.78  5168.8 1991.59  5188.8 1992.93  5258.9 1995.68  5285.7 1997.38
#Mann=3,-1,0
  4795.5    0.07       0  4992.6    0.05       0  4996.6    0.07       0
Bank Sta=4992.6,4996.6
Exp/Cntr=0.3,0.1

Type RM Length L Ch R = 1,112,0,0,0
BEGIN DESCRIPTION:
Stream0393 0.1
END DESCRIPTION:
XS GIS Cut Line= 4
      1848983.34     13964561.08      1848974.65     13964808.52
      1849024.57     13964958.26      1849260.52     13965021.04
#Sta/Elev= 30
  4660.4 1989.92  4694.3 1989.51  4757.5 1986.61  4764.4 1985.48  4874.5 1981.83
  4908.0 1980.07  4922.5 1978.20  4927.8 1978.70  4954.1 1976.42  4991.0 1976.38
  5007.7 1972.66  5007.9 1972.16  5011.4 1972.16  5011.7 1972.66  5030.8 1973.37
  5049.0 1976.38  5054.3 1977.85  5068.6 1977.64  5072.0 1979.00  5077.2 1978.85
  5107.0 1981.76  5112.2 1981.49  5128.4 1983.61  5152.3 1984.30  5227.4 1989.28
  5262.4 1990.88  5267.6 1990.57  5302.5 1992.46  5307.7 1992.20  5310.0 1992.72
#Mann=3,-1,0
  4660.4    0.07       0  5007.7    0.05       0  5011.7    0.07       0
Bank Sta=5007.7,5011.7
Exp/Cntr=0.3,0.1

Chan Stop Cuts=-1