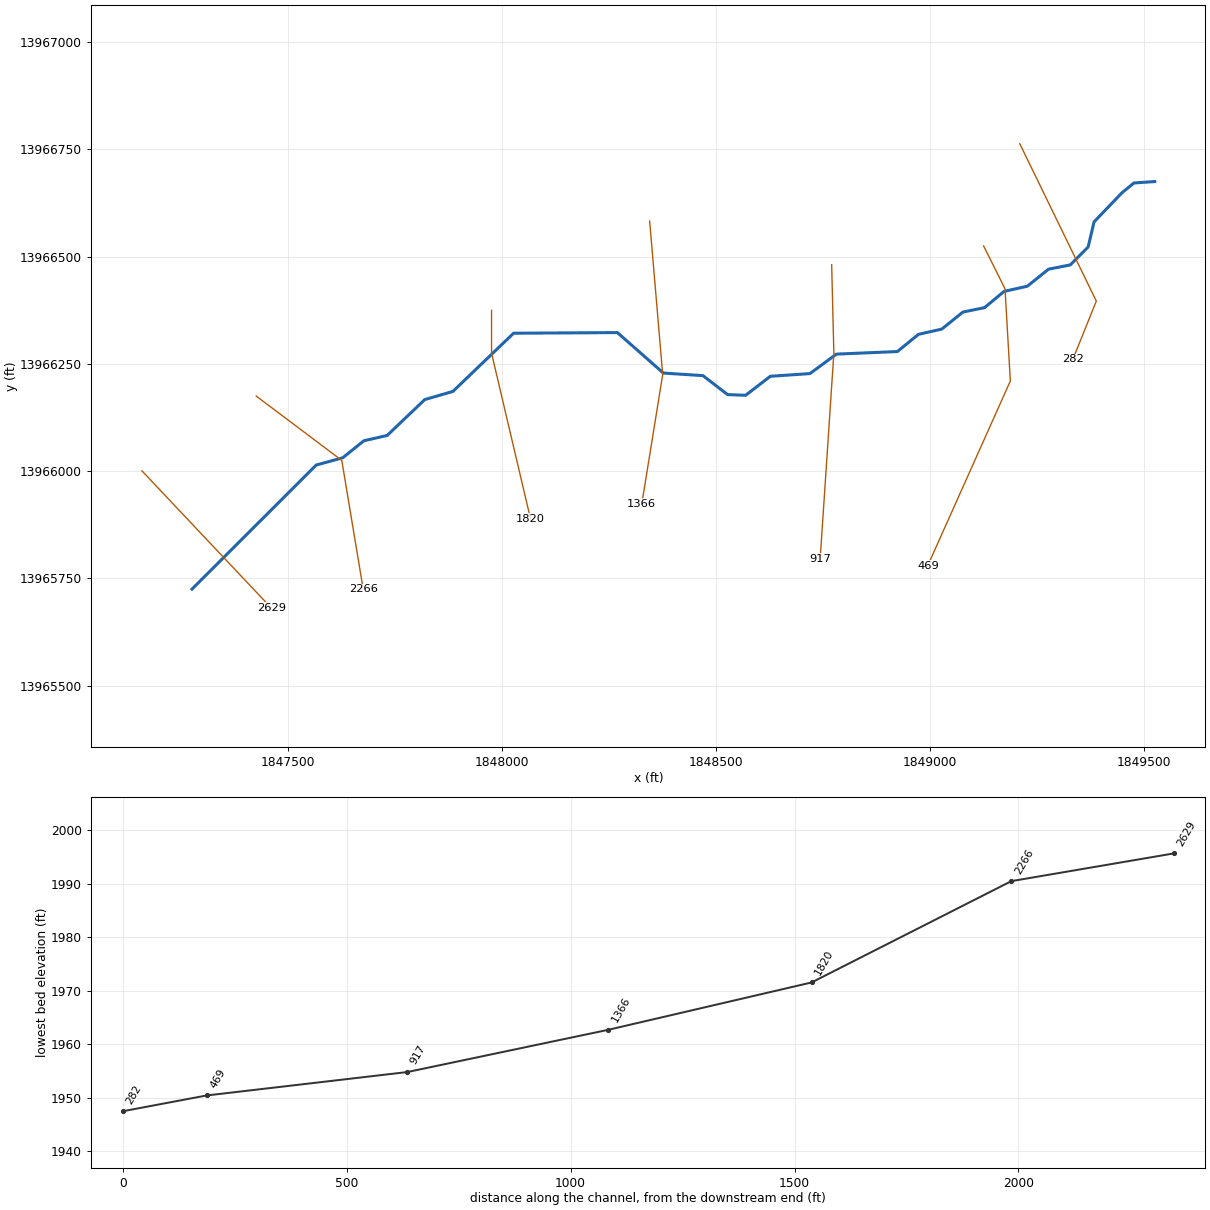
--- Stream0394.prj (project) ---

Proj Title=Stream0394 Base Level Engineering
Current Plan=p01
Default Exp/Contr=0.3,0.1
English Units
Geom File=g01
Flow File=f01
Plan File=p01
BEGIN DESCRIPTION:
Stream0394
END DESCRIPTION:

--- Stream0394.p01 (plan) ---

Plan Title=Multiple Run
Short Identifier=Multiple
Geom File=g01
Flow File=f01
Subcritical Flow
K Sum by GR= 0
Std Step Tol= 0.01
Critical Tol= 0.01
Num of Std Step Trials= 20
Max Error Tol= 0.3
Flow Tol Ratio= 0.001
Split Flow NTrial= 30
Split Flow Tol= 0.02
Split Flow Ratio= 0.02
Log Output Level= 0
Friction Slope Method= 1
Unsteady Friction Slope Method= 2
Unsteady Bridges Friction Slope Method= 1
Parabolic Critical Depth
Global Vel Dist=  1 , 1 , 1
Global Log Level= 0
CheckData=True
Encroach Param= -1, 0, 0, 0
BEGIN DESCRIPTION:
Multiple Run
END DESCRIPTION:

--- Stream0394.f01 (steady flow) ---

Flow Title=Multiple
Number of Profiles=7
Profile Names=10-year,25-year,50-year,1pct_min,100-year,1pct_plu,500-year
River Rch & RM= Stream0394,Reach-1,2629
    1128    1935    2704    1827    3645    7273    6545
Boundary for River Rch & Prof#=Stream0394,Reach-1,1
Up Type=0
Dn Type=3
Dn Slope=0.005
Boundary for River Rch & Prof#=Stream0394,Reach-1,2
Up Type=0
Dn Type=3
Dn Slope=0.005
Boundary for River Rch & Prof#=Stream0394,Reach-1,3
Up Type=0
Dn Type=3
Dn Slope=0.005
Boundary for River Rch & Prof#=Stream0394,Reach-1,4
Up Type=0
Dn Type=3
Dn Slope=0.005
Boundary for River Rch & Prof#=Stream0394,Reach-1,5
Up Type=0
Dn Type=3
Dn Slope=0.005
Boundary for River Rch & Prof#=Stream0394,Reach-1,6
Up Type=0
Dn Type=3
Dn Slope=0.005
Boundary for River Rch & Prof#=Stream0394,Reach-1,7
Up Type=0
Dn Type=3
Dn Slope=0.005

--- Stream0394.g01 (geometry) ---

Geom Title=Existing Conditions

River Reach=Stream0394,Reach-1
Reach XY= 30
      1847275.00     13965725.00      1847565.32     13966014.24
      1847627.19     13966031.10      1847676.73     13966070.81
      1847731.05     13966083.16      1847818.96     13966166.82
      1847884.68     13966185.78      1848026.46     13966321.46
      1848269.14     13966322.93      1848376.50     13966228.62
      1848469.03     13966222.62      1848526.73     13966178.37
      1848568.88     13966176.82      1848626.58     13966221.11
      1848719.02     13966227.35      1848780.94     13966272.73
      1848923.44     13966278.76      1848972.82     13966318.88
      1849027.20     13966331.08      1849076.72     13966370.84
      1849127.20     13966381.08      1849172.80     13966418.92
      1849227.20     13966431.08      1849276.76     13966470.80
      1849327.55     13966480.73      1849369.25     13966522.46
      1849383.15     13966581.05      1849448.13     13966648.68
      1849476.34     13966671.73      1849525.00     13966675.00

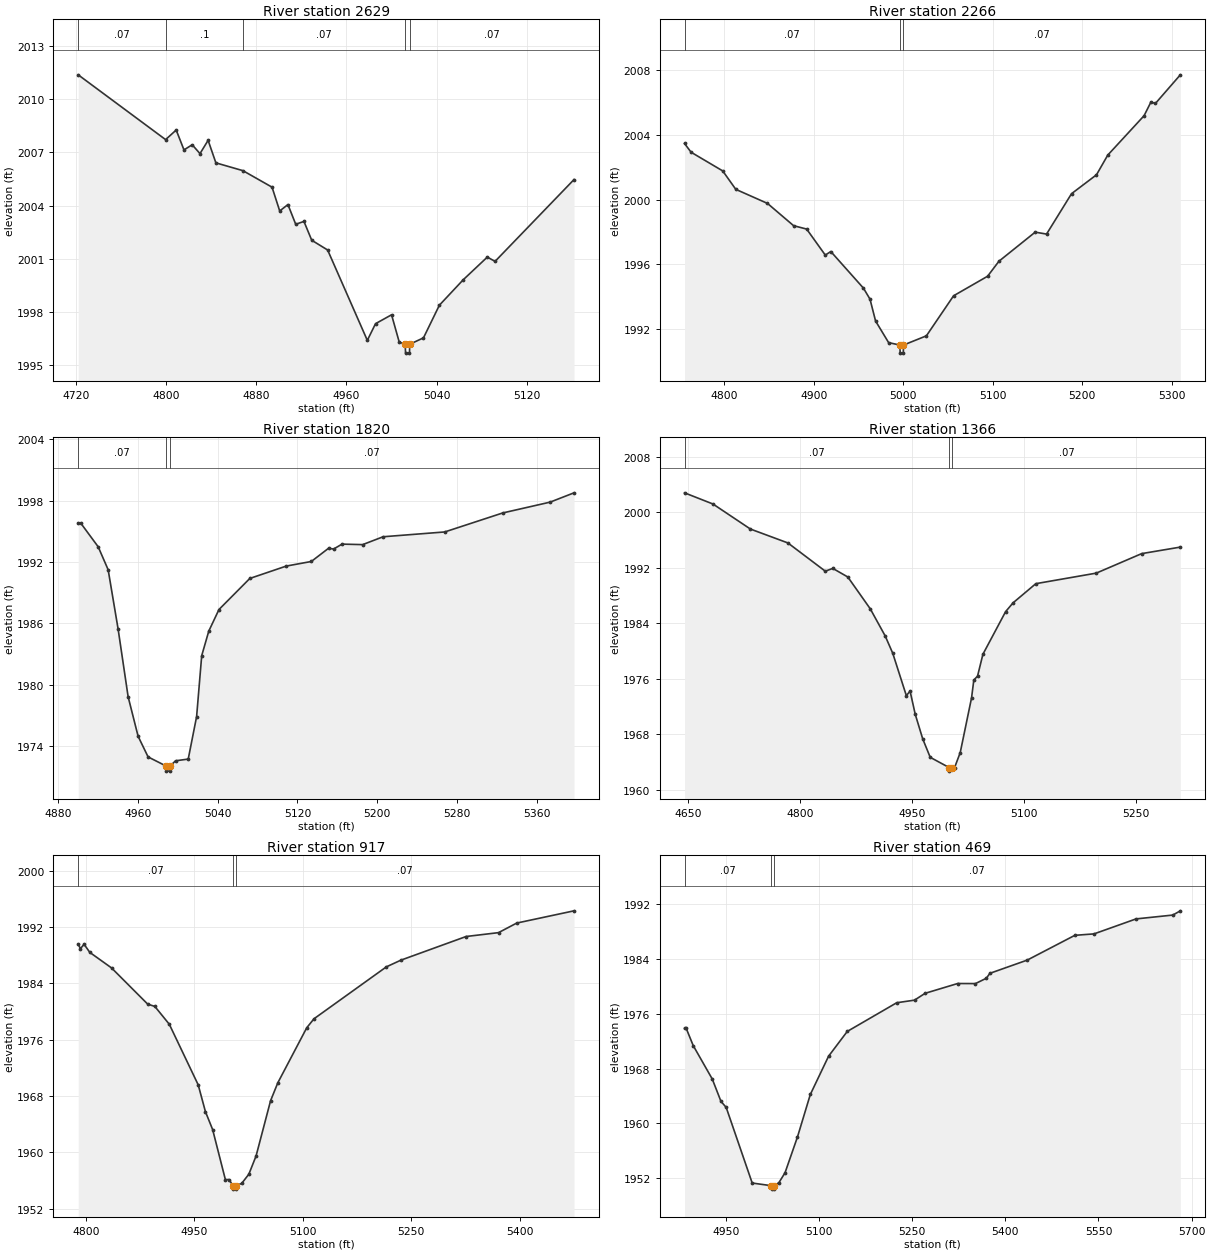
Type RM Length L Ch R = 1,2629,363,363,363
BEGIN DESCRIPTION:
Stream0394 6.0
END DESCRIPTION:
XS GIS Cut Line= 2
      1847157.93     13966000.65      1847460.04     13965681.18
#Sta/Elev= 30
  4722.2 2011.37  4799.7 2007.72  4809.1 2008.26  4816.0 2007.14  4823.3 2007.43
  4830.2 2006.93  4837.4 2007.68  4844.3 2006.41  4868.3 2005.97  4894.1 2005.04
  4900.9 2003.70  4908.2 2004.06  4915.1 2002.95  4922.4 2003.11  4929.3 2002.05
  4943.4 2001.50  4978.6 1996.41  4985.9 1997.35  5000.1 1997.85  5006.9 1996.31
  5012.2 1996.19  5012.5 1995.69  5016.0 1995.69  5016.2 1996.19  5028.4 1996.55
  5042.5 1998.39  5063.6 1999.82  5085.0 2001.10  5091.9 2000.86  5161.9 2005.47
#Mann=5,-1,0
  4722.2    0.07       0  4799.7     0.1       0  4868.3    0.07       0
  5012.2    0.05       0  5016.2    0.07       0
Bank Sta=5012.2,5016.2
Exp/Cntr=0.3,0.1

Type RM Length L Ch R = 1,2266,446,446,446
BEGIN DESCRIPTION:
Stream0394 5.0
END DESCRIPTION:
XS GIS Cut Line= 3
      1847425.01     13966175.00      1847625.00     13966025.00
      1847674.99     13965725.03
#Sta/Elev= 30
  4755.5 2003.48  4762.8 2002.94  4798.2 2001.78  4812.8 2000.64  4848.2 1999.77
  4877.4 1998.39  4892.0 1998.18  4912.8 1996.57  4919.0 1996.79  4955.5 1994.52
  4962.8 1993.84  4969.0 1992.49  4983.6 1991.15  4996.2 1991.00  4996.5 1990.50
  5000.0 1990.50  5000.2 1991.00  5025.8 1991.57  5056.2 1994.05  5094.2 1995.26
  5106.9 1996.19  5147.4 1997.99  5160.1 1997.87  5188.0 2000.37  5215.9 2001.54
  5228.5 2002.76  5269.1 2005.20  5276.7 2006.04  5281.8 2005.96  5309.6 2007.73
#Mann=3,-1,0
  4755.5    0.07       0  4996.2    0.05       0  5000.2    0.07       0
Bank Sta=4996.2,5000.2
Exp/Cntr=0.3,0.1

Type RM Length L Ch R = 1,1820,454,454,454
BEGIN DESCRIPTION:
Stream0394 4.0
END DESCRIPTION:
XS GIS Cut Line= 3
      1847975.00     13966374.95      1847975.00     13966275.00
      1848066.02     13965888.93
#Sta/Elev= 30
  4900.4 1995.82  4902.9 1995.82  4920.4 1993.50  4930.4 1991.25  4940.4 1985.43
  4950.4 1978.82  4960.4 1974.95  4970.4 1972.93  4988.4 1972.04  4988.6 1971.54
  4992.1 1971.54  4992.4 1972.04  4997.9 1972.55  5010.6 1972.72  5019.0 1976.88
  5024.1 1982.84  5031.2 1985.25  5041.4 1987.36  5072.3 1990.40  5108.8 1991.61
  5133.9 1992.06  5151.1 1993.35  5156.2 1993.28  5164.7 1993.76  5185.3 1993.71
  5205.8 1994.48  5267.5 1994.95  5325.6 1996.81  5373.1 1997.87  5397.0 1998.78
#Mann=3,-1,0
  4900.4    0.07       0  4988.4    0.05       0  4992.4    0.07       0
Bank Sta=4988.4,4992.4
Exp/Cntr=0.3,0.1

Type RM Length L Ch R = 1,1366,449,449,449
BEGIN DESCRIPTION:
Stream0394 3.0
END DESCRIPTION:
XS GIS Cut Line= 3
      1848344.49     13966582.96      1848375.00     13966225.00
      1848326.20     13965923.89
#Sta/Elev= 30
  4645.3 2002.78  4683.4 2001.17  4733.6 1997.56  4783.8 1995.56  4833.9 1991.49
  4844.0 1991.89  4864.1 1990.65  4894.2 1986.06  4914.2 1982.15  4924.3 1979.66
  4942.5 1973.56  4947.5 1974.21  4954.4 1970.88  4964.4 1967.34  4974.5 1964.67
  5000.1 1963.18  5000.3 1962.68  5004.1 1963.18  5007.1 1963.18  5014.7 1965.35
  5029.9 1973.25  5032.9 1975.80  5037.9 1976.37  5045.1 1979.52  5075.5 1985.66
  5085.6 1986.94  5116.0 1989.69  5197.0 1991.21  5257.8 1994.02  5309.6 1994.96
#Mann=3,-1,0
  4645.3    0.07       0  5000.1    0.05       0  5004.1    0.07       0
Bank Sta=5000.1,5004.1
Exp/Cntr=0.3,0.1

Type RM Length L Ch R = 1,917,448,448,448
BEGIN DESCRIPTION:
Stream0394 2.0
END DESCRIPTION:
XS GIS Cut Line= 3
      1848769.87     13966481.09      1848775.00     13966275.00
      1848743.04     13965795.92
#Sta/Elev= 30
  4789.1 1989.58  4792.2 1988.94  4797.2 1989.57  4805.2 1988.41  4835.2 1986.21
  4885.2 1981.07  4895.2 1980.73  4915.2 1978.20  4955.2 1969.59  4965.2 1965.78
  4975.2 1963.23  4992.8 1956.13  4997.8 1956.13  5003.3 1955.27  5003.5 1954.77
  5007.0 1954.77  5007.3 1955.27  5015.3 1955.57  5025.3 1956.89  5035.3 1959.48
  5055.4 1967.34  5065.4 1969.88  5105.5 1977.71  5115.5 1978.98  5215.7 1986.36
  5235.8 1987.31  5326.0 1990.67  5370.9 1991.22  5396.1 1992.58  5475.4 1994.32
#Mann=3,-1,0
  4789.1    0.07       0  5003.3    0.05       0  5007.3    0.07       0
Bank Sta=5003.3,5007.3
Exp/Cntr=0.3,0.1

Type RM Length L Ch R = 1,469,187,187,187
BEGIN DESCRIPTION:
Stream0394 1.0
END DESCRIPTION:
XS GIS Cut Line= 4
      1849124.99     13966525.02      1849175.00     13966425.00
      1849187.45     13966210.09      1848994.58     13965779.94
#Sta/Elev= 30
  4883.3 1973.86  4886.1 1973.86  4897.3 1971.36  4928.0 1966.47  4942.0 1963.21
  4950.4 1962.33  4992.3 1951.28  5023.2 1950.89  5023.4 1950.39  5026.9 1950.39
  5027.2 1950.89  5035.2 1951.32  5045.2 1952.79  5065.2 1958.01  5085.9 1964.22
  5115.3 1969.81  5145.4 1973.43  5225.0 1977.62  5253.7 1978.00  5270.8 1979.00
  5323.2 1980.43  5351.9 1980.42  5369.4 1981.20  5375.1 1981.92  5435.2 1983.85
  5511.9 1987.47  5542.8 1987.68  5610.5 1989.87  5669.7 1990.43  5681.8 1991.05
#Mann=3,-1,0
  4883.3    0.07       0  5023.2    0.05       0  5027.2    0.07       0
Bank Sta=5023.2,5027.2
Exp/Cntr=0.3,0.1

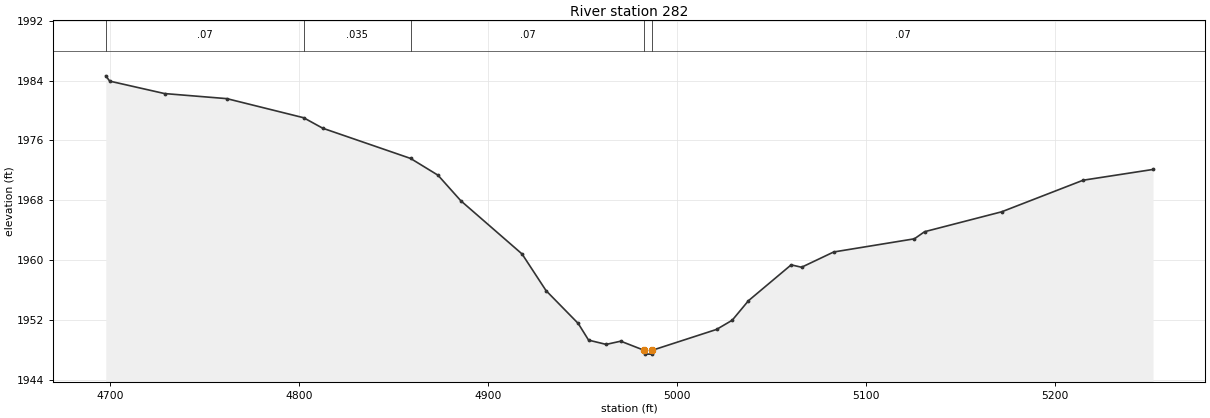
Type RM Length L Ch R = 1,282,0,0,0
BEGIN DESCRIPTION:
Stream0394 0.0
END DESCRIPTION:
XS GIS Cut Line= 3
      1849209.62     13966762.99      1849388.38     13966396.28
      1849333.57     13966260.70
#Sta/Elev= 30
  4697.9 1984.63  4700.0 1983.92  4729.0 1982.26  4762.0 1981.58  4802.6 1979.03
  4812.7 1977.63  4859.2 1973.59  4873.7 1971.35  4885.8 1967.93  4918.2 1960.82
  4930.9 1955.92  4947.9 1951.54  4953.4 1949.31  4962.7 1948.74  4970.4 1949.17
  4982.9 1947.94  4983.2 1947.44  4986.7 1947.44  4986.9 1947.94  5021.1 1950.74
  5029.4 1951.97  5038.0 1954.58  5060.6 1959.37  5066.1 1959.05  5083.1 1961.09
  5125.8 1962.85  5131.2 1963.80  5172.0 1966.46  5215.1 1970.68  5252.1 1972.12
#Mann=5,-1,0
  4697.9    0.07       0  4802.6   0.035       0  4859.2    0.07       0
  4982.9    0.05       0  4986.9    0.07       0
Bank Sta=4982.9,4986.9
Exp/Cntr=0.3,0.1

Chan Stop Cuts=-1