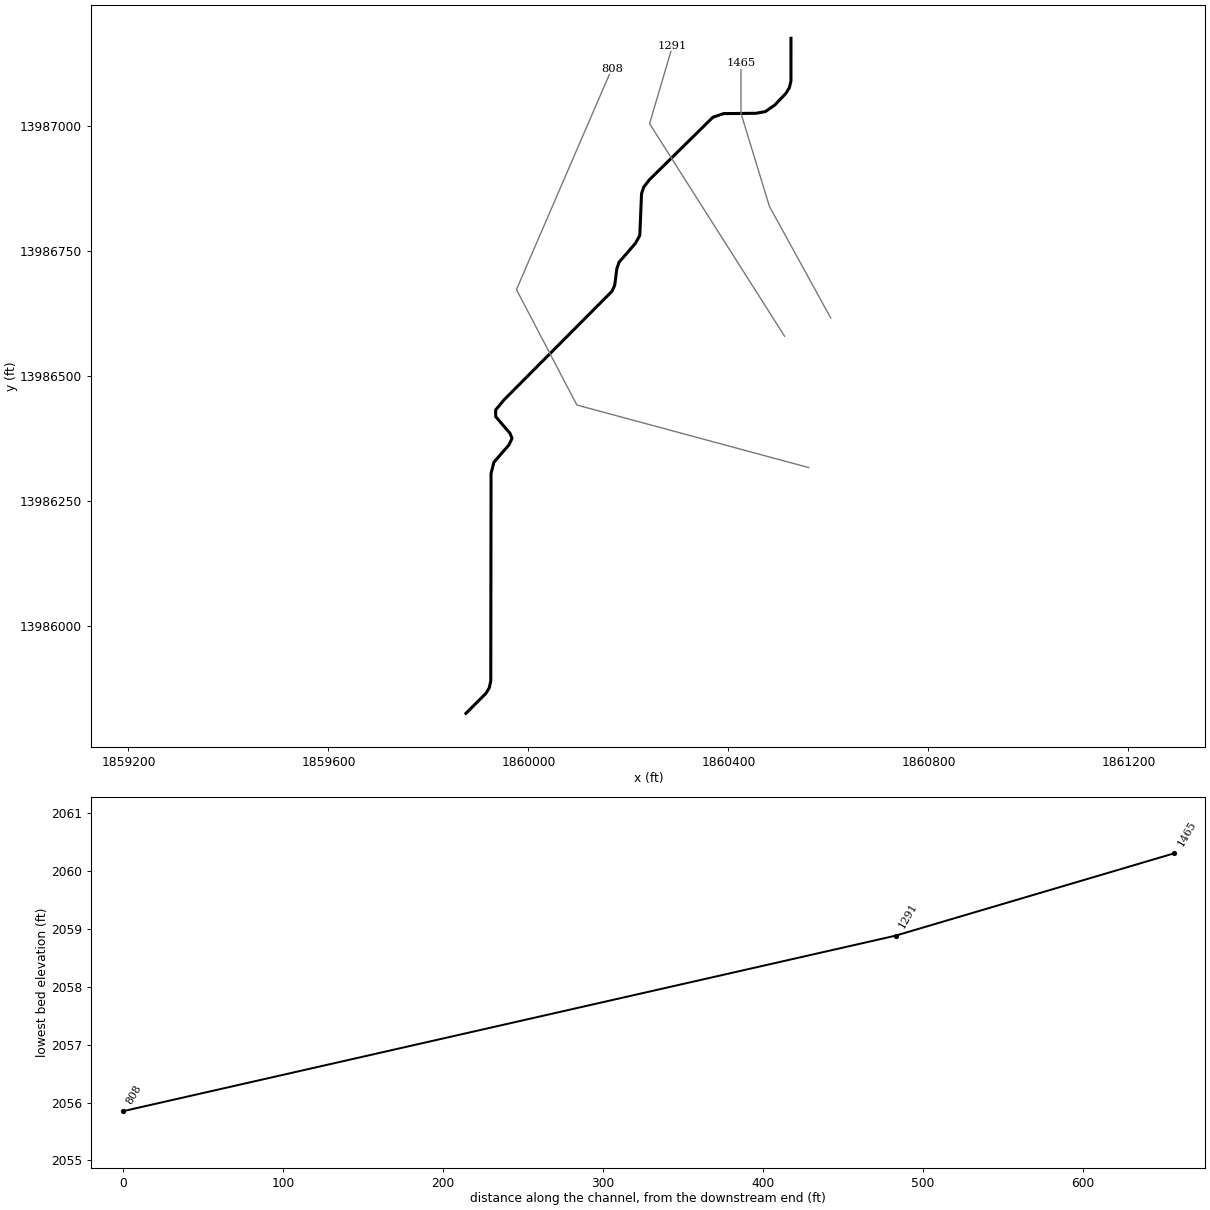
--- Stream0397.prj (project) ---

Proj Title=Stream0397 Base Level Engineering
Current Plan=p01
Default Exp/Contr=0.3,0.1
English Units
Geom File=g01
Flow File=f01
Plan File=p01
Y Axis Title=Elevation
X Axis Title(PF)=Main Channel Distance
X Axis Title(XS)=Station
BEGIN DESCRIPTION:
Stream0397
END DESCRIPTION:
DSS Export Rating Curves= 0
DSS Export Rating Curve Sorted= 0
DSS Export Volume Flow Curves= 0
DXF OffsetX= 0
DXF OffsetY= 0
DXF ScaleX= 1
DXF ScaleY= 10

--- Stream0397.p01 (plan) ---

Plan Title=Multiple Run
Short Identifier=Multiple
Geom File=g01
Flow File=f01
Subcritical Flow
K Sum by GR= 0
Std Step Tol= 0.01
Critical Tol= 0.01
Num of Std Step Trials= 20
Max Error Tol= 0.3
Flow Tol Ratio= 0.001
Split Flow NTrial= 30
Split Flow Tol= 0.02
Split Flow Ratio= 0.02
Log Output Level= 0
Friction Slope Method= 1
Unsteady Friction Slope Method= 2
Unsteady Bridges Friction Slope Method= 1
Parabolic Critical Depth
Global Vel Dist=  1 , 1 , 1
Global Log Level= 0
CheckData=True
Encroach Param= -1, 0, 0, 0
BEGIN DESCRIPTION:
Multiple Run
END DESCRIPTION:

--- Stream0397.f01 (steady flow) ---

Flow Title=Multiple
Program Version=4.10
Number of Profiles= 7
Profile Names=10-year,25-year,50-year,1pct_min,100-year,1pct_plu,500-year
River Rch & RM=Stream0397,Reach-1         ,1465
     654    1079    1469     968    1932    3855    3298
Boundary for River Rch & Prof#=Stream0397,Reach-1         , 1
Up Type= 0
Dn Type= 3
Dn Slope=0.007
Boundary for River Rch & Prof#=Stream0397,Reach-1         , 2
Up Type= 0
Dn Type= 3
Dn Slope=0.007
Boundary for River Rch & Prof#=Stream0397,Reach-1         , 3
Up Type= 0
Dn Type= 3
Dn Slope=0.007
Boundary for River Rch & Prof#=Stream0397,Reach-1         , 4
Up Type= 0
Dn Type= 3
Dn Slope=0.007
Boundary for River Rch & Prof#=Stream0397,Reach-1         , 5
Up Type= 0
Dn Type= 3
Dn Slope=0.007
Boundary for River Rch & Prof#=Stream0397,Reach-1         , 6
Up Type= 0
Dn Type= 3
Dn Slope=0.007
Boundary for River Rch & Prof#=Stream0397,Reach-1         , 7
Up Type= 0
Dn Type= 3
Dn Slope=0.007
DSS Import GetInterval= 0
DSS Import GetPeak= 0
DSS Import FillOption= 0

--- Stream0397.g01 (geometry) ---

Geom Title=Existing Conditions

River Reach=Stream0397,Reach-1
Reach XY= 30
      1860525.00     13987175.00      1860524.96     13987089.87
      1860521.74     13987076.12      1860514.74     13987064.76
      1860492.21     13987041.24      1860473.74     13987028.50
      1860455.06     13987025.09      1860390.22     13987024.47
      1860368.83     13987017.14      1860241.46     13986891.75
      1860230.52     13986877.43      1860226.16     13986864.52
      1860222.67     13986780.97      1860214.16     13986765.35
      1860181.14     13986727.17      1860176.72     13986714.29
      1860172.50     13986681.03      1860166.86     13986668.94
      1859950.77     13986451.67      1859934.30     13986431.67
      1859934.60     13986418.34      1859963.15     13986385.06
      1859967.19     13986375.10      1859960.93     13986361.84
      1859931.00     13986327.45      1859925.18     13986305.02
      1859924.64     13985890.15      1859921.71     13985876.36
      1859914.95     13985865.02      1859875.00     13985825.00

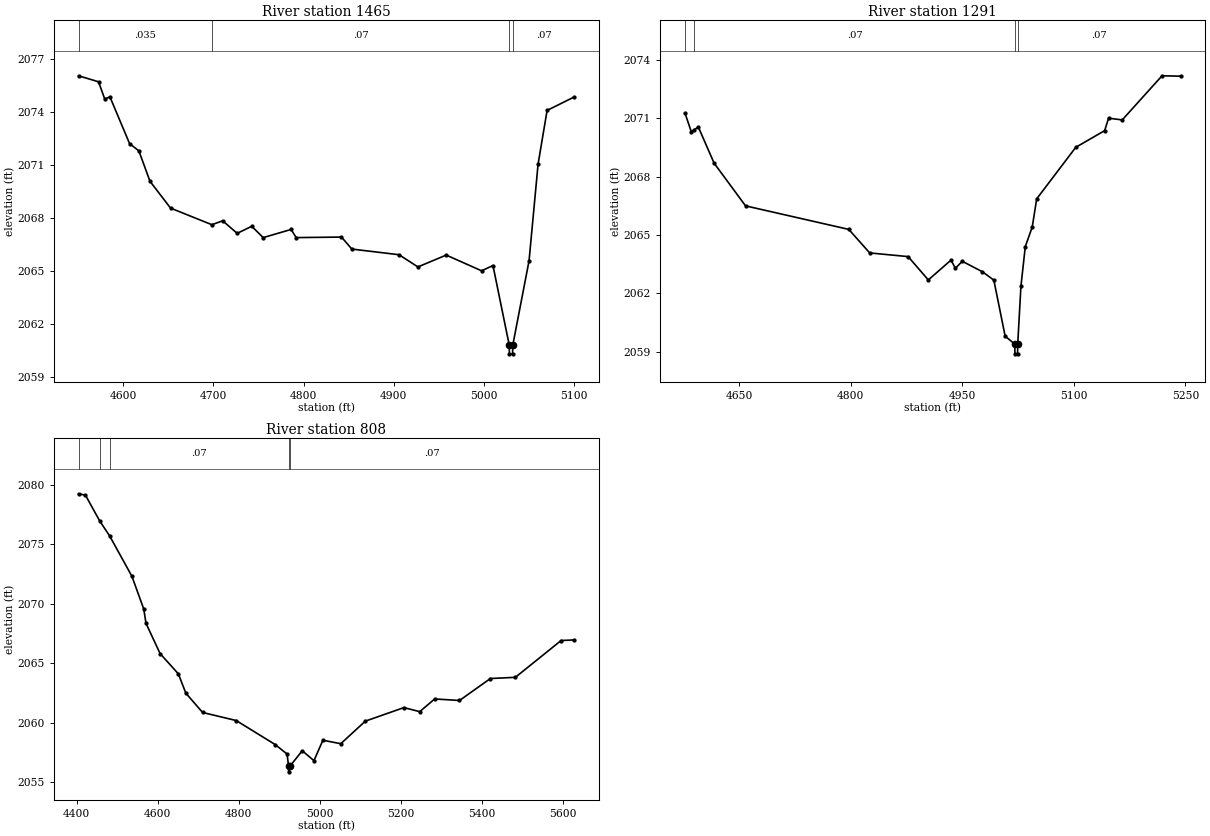
Type RM Length L Ch R = 1,1465,174,174,174
BEGIN DESCRIPTION:
Stream0397 1.0
END DESCRIPTION:
XS GIS Cut Line= 4
      1860604.56     13986615.57      1860482.01     13986838.70
      1860425.00     13987025.00      1860425.00     13987125.00
#Sta/Elev= 30
  4550.6 2076.04  4572.8 2075.70  4579.7 2074.72  4585.4 2074.85  4607.2 2072.20
  4617.5 2071.79  4629.8 2070.07  4652.6 2068.55  4698.4 2067.61  4710.4 2067.83
  4726.5 2067.12  4742.6 2067.52  4755.3 2066.88  4786.2 2067.34  4791.9 2066.88
  4842.1 2066.91  4853.6 2066.23  4905.9 2065.91  4926.8 2065.22  4958.2 2065.89
  4997.4 2065.00  5010.0 2065.30  5028.0 2060.80  5028.2 2060.30  5031.7 2060.30
  5032.0 2060.80  5050.0 2065.57  5060.0 2071.04  5070.0 2074.08  5100.0 2074.84
#Mann=4,-1,0
  4550.6   0.035       0  4698.4    0.07       0  5028.0    0.05       0
  5032.0    0.07       0
Bank Sta=5028,5032
Exp/Cntr=0.3,0.1

Type RM Length L Ch R = 1,1291,483,483,483
BEGIN DESCRIPTION:
Stream0397 0.1
END DESCRIPTION:
XS GIS Cut Line= 3
      1860512.30     13986579.11      1860242.23     13987004.31
      1860288.15     13987160.26
#Sta/Elev= 30
  4577.3 2071.26  4585.9 2070.29  4589.9 2070.40  4595.2 2070.55  4616.4 2068.69
  4658.7 2066.49  4797.5 2065.28  4825.6 2064.07  4877.3 2063.88  4904.4 2062.68
  4934.9 2063.70  4940.8 2063.28  4950.1 2063.64  4977.2 2063.10  4992.5 2062.67
  5007.7 2059.79  5020.6 2059.38  5020.9 2058.88  5024.4 2058.88  5024.6 2059.38
  5028.9 2062.35  5034.8 2064.40  5044.1 2065.40  5050.1 2066.85  5102.6 2069.50
  5141.5 2070.36  5146.7 2071.00  5165.1 2070.91  5218.6 2073.18  5243.6 2073.16
#Mann=4,-1,0
  4577.3   0.035       0  4589.9    0.07       0  5020.6    0.05       0
  5024.6    0.07       0
Bank Sta=5020.6,5024.6
Exp/Cntr=0.3,0.1

Type RM Length L Ch R = 1,808,0,0,0
BEGIN DESCRIPTION:
Stream0397 0.0
END DESCRIPTION:
XS GIS Cut Line= 4
      1860560.47     13986316.59      1860096.82     13986441.68
      1859975.98     13986672.59      1860166.89     13987114.58
#Sta/Elev= 30
  4404.8 2079.27  4422.0 2079.15  4457.4 2076.96  4481.4 2075.73  4536.5 2072.32
  4565.8 2069.55  4571.2 2068.36  4606.0 2065.81  4651.1 2064.10  4669.4 2062.48
  4710.8 2060.85  4793.7 2060.17  4889.7 2058.15  4919.1 2057.35  4922.8 2056.35
  4923.0 2055.85  4926.8 2056.35  4956.5 2057.63  4985.4 2056.79  5007.4 2058.51
  5051.6 2058.22  5112.1 2060.12  5207.2 2061.26  5246.3 2060.92  5283.2 2061.99
  5344.3 2061.86  5420.6 2063.71  5482.1 2063.81  5594.9 2066.91  5627.1 2066.96
#Mann=5,-1,0
  4404.8    0.07       0  4457.4   0.035       0  4481.4    0.07       0
  4922.8    0.05       0  4926.8    0.07       0
Bank Sta=4922.8,4926.8
Exp/Cntr=0.3,0.1

Chan Stop Cuts=-1