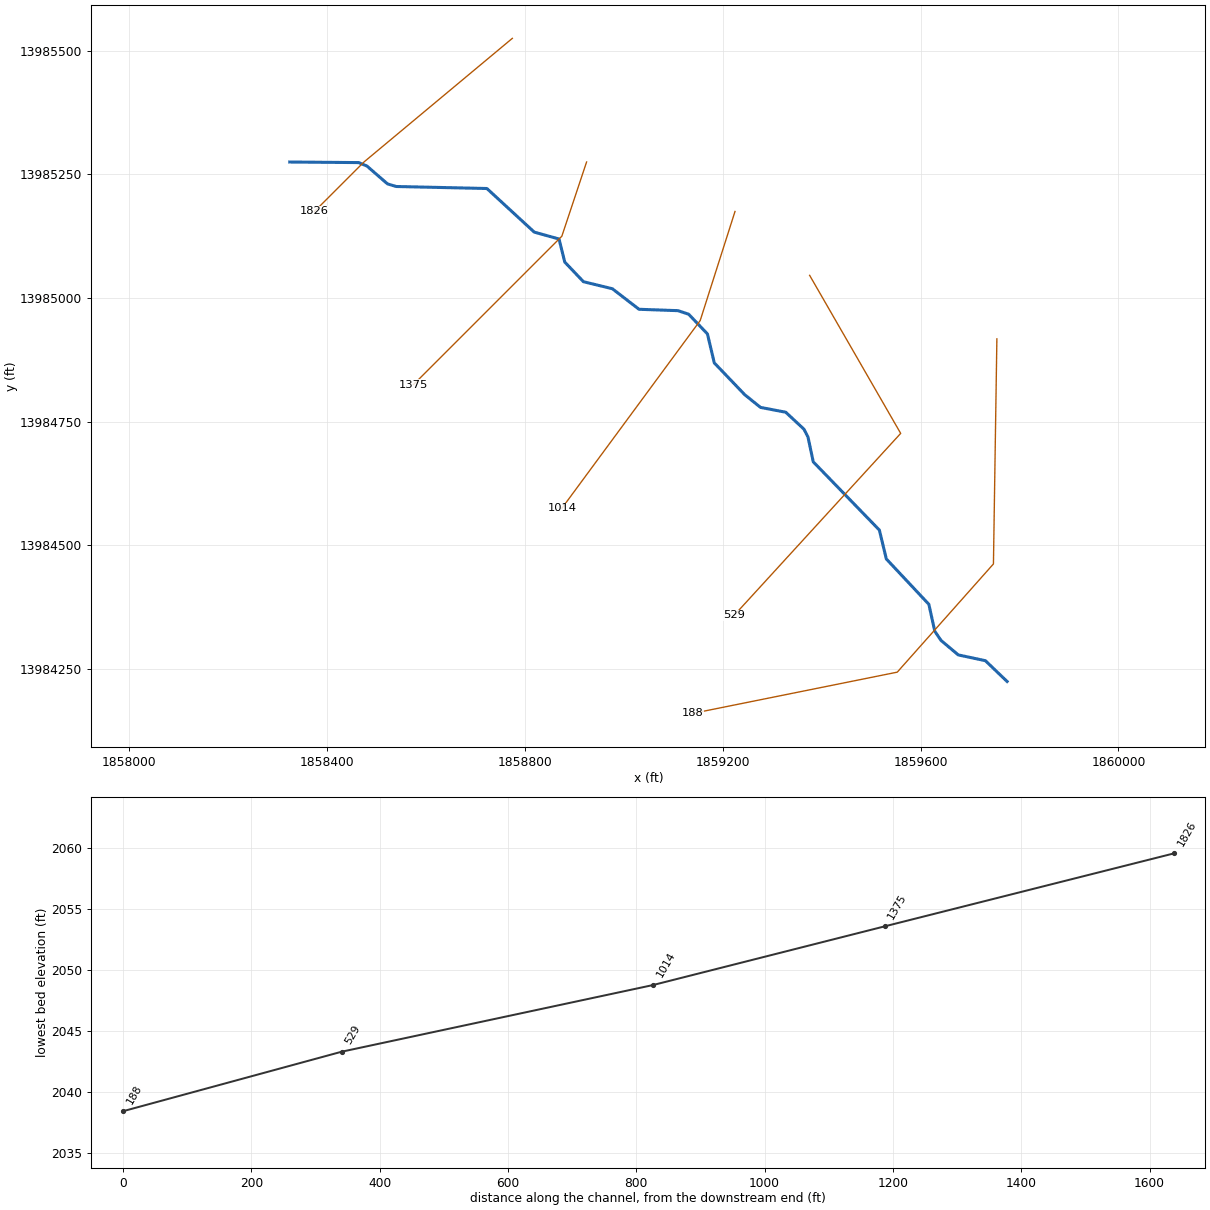
--- Stream0398.prj (project) ---

Proj Title=Stream0398 Base Level Engineering
Current Plan=p01
Default Exp/Contr=0.3,0.1
English Units
Geom File=g01
Flow File=f01
Plan File=p01
BEGIN DESCRIPTION:
Stream0398
END DESCRIPTION:

--- Stream0398.p01 (plan) ---

Plan Title=Multiple Run
Short Identifier=Multiple
Geom File=g01
Flow File=f01
Subcritical Flow
K Sum by GR= 0
Std Step Tol= 0.01
Critical Tol= 0.01
Num of Std Step Trials= 20
Max Error Tol= 0.3
Flow Tol Ratio= 0.001
Split Flow NTrial= 30
Split Flow Tol= 0.02
Split Flow Ratio= 0.02
Log Output Level= 0
Friction Slope Method= 1
Unsteady Friction Slope Method= 2
Unsteady Bridges Friction Slope Method= 1
Parabolic Critical Depth
Global Vel Dist=  1 , 1 , 1
Global Log Level= 0
CheckData=True
Encroach Param= -1, 0, 0, 0
BEGIN DESCRIPTION:
Multiple Run
END DESCRIPTION:

--- Stream0398.f01 (steady flow) ---

Flow Title=Multiple
Number of Profiles=7
Profile Names=10-year,25-year,50-year,1pct_min,100-year,1pct_plu,500-year
River Rch & RM= Stream0398,Reach-1,1826
     560     916    1242     816    1627    3247    2755
Boundary for River Rch & Prof#=Stream0398,Reach-1,1
Up Type=0
Dn Type=3
Dn Slope=0.005
Boundary for River Rch & Prof#=Stream0398,Reach-1,2
Up Type=0
Dn Type=3
Dn Slope=0.005
Boundary for River Rch & Prof#=Stream0398,Reach-1,3
Up Type=0
Dn Type=3
Dn Slope=0.005
Boundary for River Rch & Prof#=Stream0398,Reach-1,4
Up Type=0
Dn Type=3
Dn Slope=0.005
Boundary for River Rch & Prof#=Stream0398,Reach-1,5
Up Type=0
Dn Type=3
Dn Slope=0.005
Boundary for River Rch & Prof#=Stream0398,Reach-1,6
Up Type=0
Dn Type=3
Dn Slope=0.005
Boundary for River Rch & Prof#=Stream0398,Reach-1,7
Up Type=0
Dn Type=3
Dn Slope=0.005

--- Stream0398.g01 (geometry) ---

Geom Title=Existing Conditions

River Reach=Stream0398,Reach-1
Reach XY= 30
      1858325.00     13985275.00      1858464.52     13985273.83
      1858481.06     13985266.87      1858522.66     13985230.74
      1858540.22     13985225.52      1858723.53     13985221.45
      1858819.26     13985133.30      1858869.37     13985119.35
      1858880.89     13985072.79      1858918.68     13985033.07
      1858977.15     13985018.85      1859030.97     13984977.33
      1859109.91     13984974.53      1859131.45     13984967.26
      1859169.26     13984927.57      1859183.16     13984868.96
      1859244.77     13984804.59      1859276.66     13984778.98
      1859327.54     13984769.25      1859364.35     13984735.00
      1859372.54     13984719.13      1859383.17     13984668.97
      1859516.84     13984531.05      1859530.87     13984472.72
      1859616.82     13984381.02      1859628.88     13984326.43
      1859641.48     13984307.94      1859676.34     13984278.71
      1859731.11     13984267.05      1859775.00     13984225.00

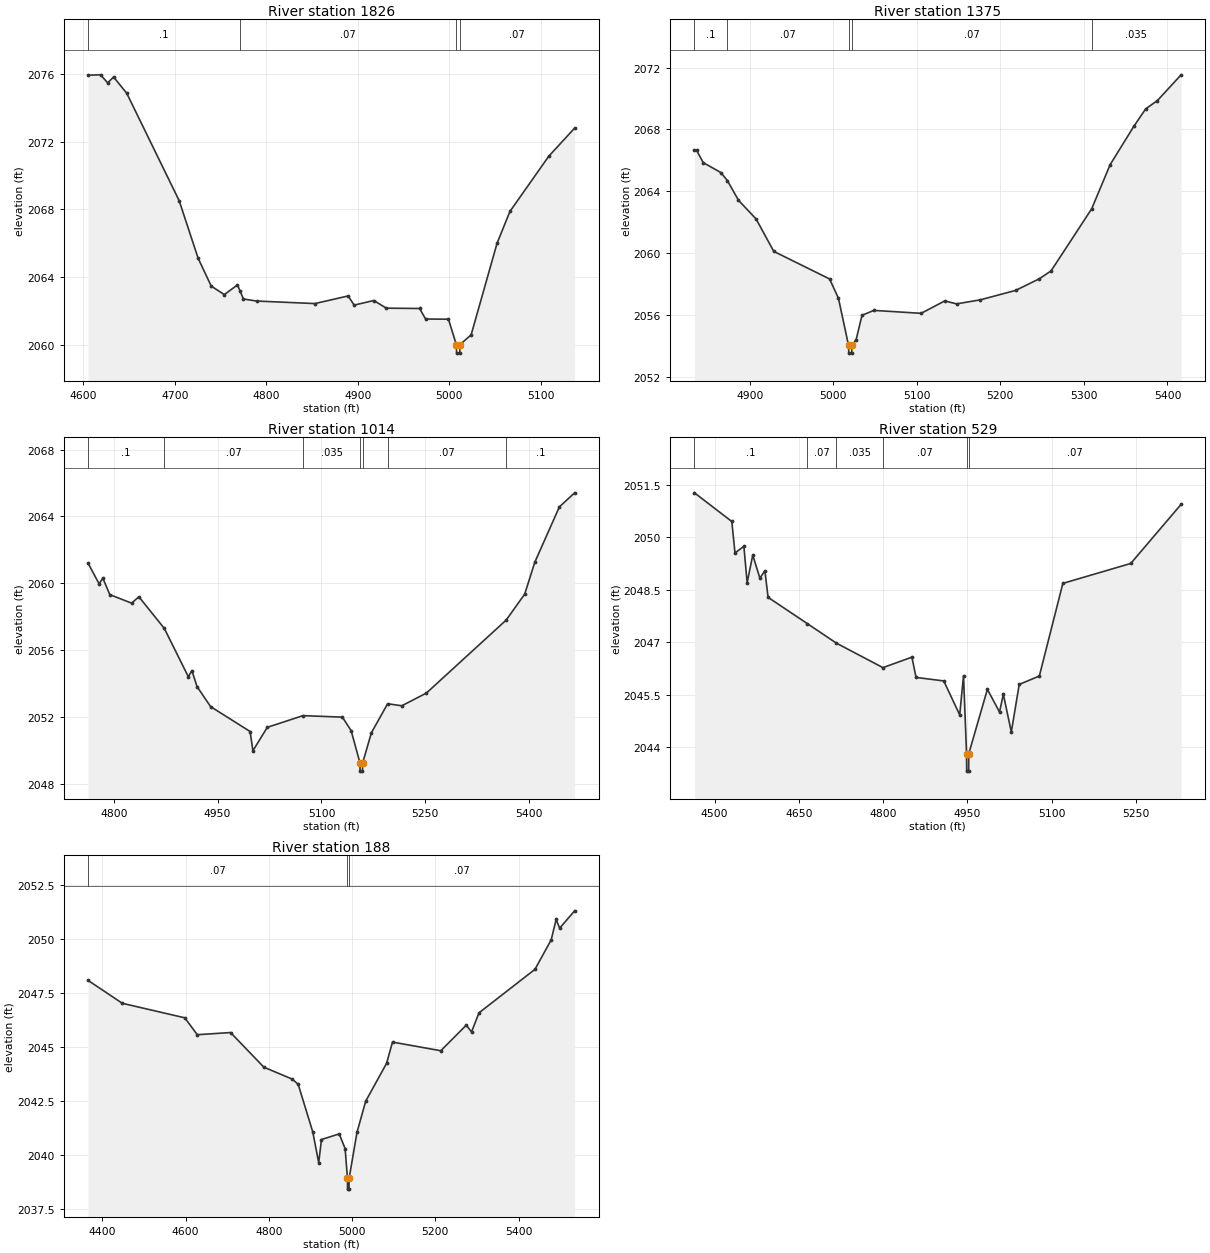
Type RM Length L Ch R = 1,1826,451,451,451
BEGIN DESCRIPTION:
Stream0398 3.0
END DESCRIPTION:
XS GIS Cut Line= 3
      1858774.99     13985524.99      1858475.00     13985275.00
      1858375.02     13985175.02
#Sta/Elev= 30
  4605.0 2075.91  4618.7 2075.93  4626.5 2075.46  4633.0 2075.80  4647.3 2074.85
  4704.6 2068.52  4725.4 2065.12  4739.7 2063.48  4754.0 2062.98  4768.4 2063.55
  4771.3 2063.18  4774.9 2062.72  4789.2 2062.60  4853.0 2062.45  4889.4 2062.90
  4895.9 2062.36  4917.4 2062.63  4931.1 2062.18  4967.5 2062.16  4974.0 2061.54
  4999.0 2061.53  5007.6 2060.03  5007.9 2059.53  5011.4 2059.53  5011.6 2060.03
  5023.8 2060.61  5052.1 2066.00  5066.2 2067.88  5108.6 2071.13  5136.9 2072.79
#Mann=4,-1,0
  4605.0     0.1       0  4771.3    0.07       0  5007.6    0.05       0
  5011.6    0.07       0
Bank Sta=5007.6,5011.6
Exp/Cntr=0.3,0.1

Type RM Length L Ch R = 1,1375,361,361,361
BEGIN DESCRIPTION:
Stream0398 2.0
END DESCRIPTION:
XS GIS Cut Line= 3
      1858925.00     13985275.00      1858875.00     13985125.00
      1858574.99     13984824.99
#Sta/Elev= 30
  4833.9 2066.65  4836.5 2066.65  4844.4 2065.86  4865.5 2065.22  4873.3 2064.70
  4886.6 2063.43  4907.7 2062.22  4928.8 2060.13  4995.6 2058.35  5006.2 2057.11
  5018.3 2054.06  5018.6 2053.56  5022.1 2053.56  5022.3 2054.06  5027.4 2054.43
  5034.4 2056.00  5048.6 2056.32  5105.2 2056.13  5133.4 2056.93  5147.6 2056.74
  5175.9 2057.00  5218.3 2057.61  5246.6 2058.36  5260.7 2058.87  5309.3 2062.88
  5331.4 2065.73  5359.7 2068.20  5373.9 2069.33  5388.0 2069.87  5416.3 2071.53
#Mann=5,-1,0
  4833.9     0.1       0  4873.3    0.07       0  5018.3    0.05       0
  5022.3    0.07       0  5309.3   0.035       0
Bank Sta=5018.3,5022.3
Exp/Cntr=0.3,0.1

Type RM Length L Ch R = 1,1014,485,485,485
BEGIN DESCRIPTION:
Stream0398 1.0
END DESCRIPTION:
XS GIS Cut Line= 3
      1859225.01     13985175.02      1859154.67     13984954.58
      1858874.99     13984574.98
#Sta/Elev= 30
  4762.8 2061.21  4778.9 2059.96  4784.2 2060.31  4794.3 2059.32  4825.8 2058.81
  4836.3 2059.19  4873.0 2057.30  4907.7 2054.41  4912.9 2054.77  4920.3 2053.82
  4939.9 2052.62  4997.0 2051.13  5001.0 2049.98  5021.8 2051.38  5073.3 2052.08
  5130.3 2051.99  5142.9 2051.18  5155.6 2049.26  5155.8 2048.76  5159.3 2048.76
  5159.6 2049.26  5172.2 2051.06  5195.6 2052.79  5216.1 2052.67  5251.6 2053.43
  5366.9 2057.80  5393.6 2059.35  5408.2 2061.26  5443.7 2064.57  5465.7 2065.41
#Mann=7,-1,0
  4762.8     0.1       0  4873.0    0.07       0  5073.3   0.035       0
  5155.6    0.05       0  5159.6   0.035       0  5195.6    0.07       0
  5366.9     0.1       0
Bank Sta=5155.6,5159.6
Exp/Cntr=0.3,0.1

Type RM Length L Ch R = 1,529,341,341,341
BEGIN DESCRIPTION:
Stream0398 0.0
END DESCRIPTION:
XS GIS Cut Line= 3
      1859375.87     13985045.94      1859559.89     13984726.50
      1859223.80     13984359.22
#Sta/Elev= 30
  4464.0 2051.27  4530.5 2050.45  4536.2 2049.55  4552.0 2049.74  4557.8 2048.70
  4567.8 2049.49  4580.5 2048.83  4589.4 2049.04  4595.1 2048.28  4664.9 2047.53
  4716.8 2046.97  4799.6 2046.27  4851.2 2046.57  4858.6 2045.99  4907.9 2045.89
  4936.3 2044.92  4943.1 2046.04  4948.5 2043.81  4948.7 2043.31  4952.2 2043.31
  4952.5 2043.81  4985.6 2045.65  5007.2 2045.00  5014.0 2045.51  5028.2 2044.43
  5042.3 2045.79  5078.1 2046.03  5120.0 2048.68  5240.9 2049.25  5330.5 2050.94
#Mann=6,-1,0
  4464.0     0.1       0  4664.9    0.07       0  4716.8   0.035       0
  4799.6    0.07       0  4948.5    0.05       0  4952.5    0.07       0
Bank Sta=4948.5,4952.5
Exp/Cntr=0.3,0.1

Type RM Length L Ch R = 1,188,0,0,0
BEGIN DESCRIPTION:
Stream0398 4.0
END DESCRIPTION:
XS GIS Cut Line= 4
      1859754.34     13984917.46      1859747.39     13984462.61
      1859552.95     13984243.86      1859139.85     13984160.55
#Sta/Elev= 30
  4365.7 2048.08  4448.2 2047.02  4598.2 2046.35  4628.2 2045.57  4708.2 2045.67
  4788.2 2044.07  4856.3 2043.52  4870.6 2043.28  4905.7 2041.08  4919.9 2039.66
  4926.6 2040.73  4969.2 2040.99  4983.4 2040.31  4989.0 2038.94  4989.2 2038.44
  4992.7 2038.44  4993.0 2038.94  5011.9 2041.06  5032.8 2042.50  5083.0 2044.25
  5097.2 2045.23  5213.2 2044.83  5274.4 2046.01  5287.1 2045.70  5305.0 2046.58
  5439.5 2048.59  5478.4 2049.95  5490.3 2050.89  5498.8 2050.49  5534.7 2051.29
#Mann=3,-1,0
  4365.7    0.07       0  4989.0    0.05       0  4993.0    0.07       0
Bank Sta=4989,4993
Exp/Cntr=0.3,0.1

Chan Stop Cuts=-1