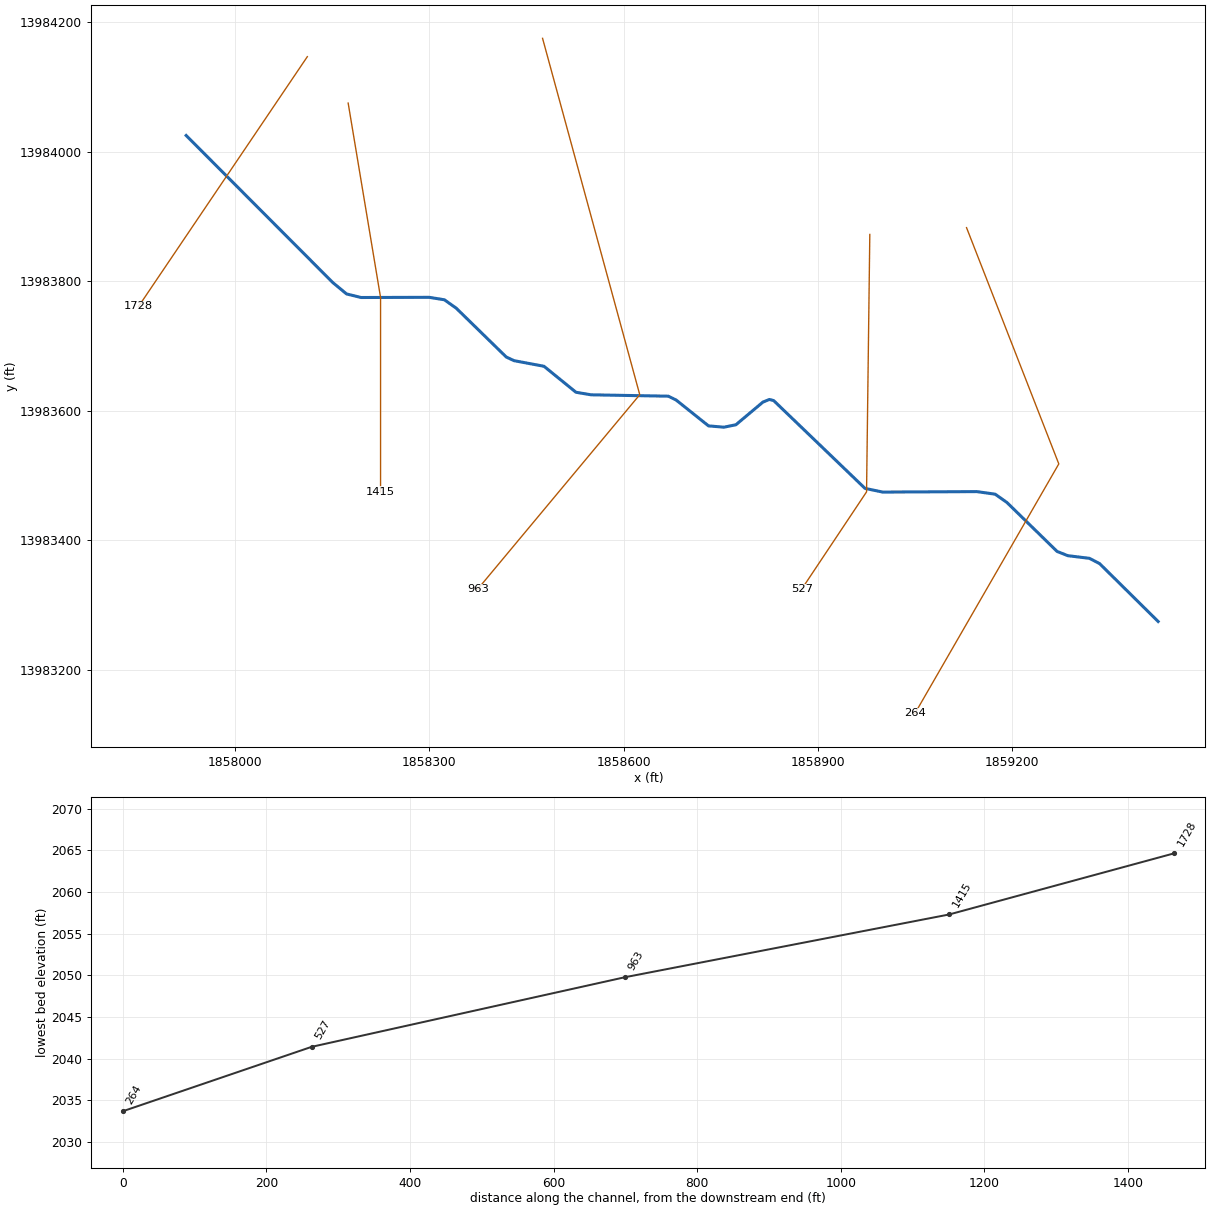
--- Stream0399.prj (project) ---

Proj Title=Stream0399 Base Level Engineering
Current Plan=p01
Default Exp/Contr=0.3,0.1
English Units
Geom File=g01
Flow File=f01
Plan File=p01
BEGIN DESCRIPTION:
Stream0399
END DESCRIPTION:

--- Stream0399.p01 (plan) ---

Plan Title=Multiple Run
Short Identifier=Multiple
Geom File=g01
Flow File=f01
Subcritical Flow
K Sum by GR= 0
Std Step Tol= 0.01
Critical Tol= 0.01
Num of Std Step Trials= 20
Max Error Tol= 0.3
Flow Tol Ratio= 0.001
Split Flow NTrial= 30
Split Flow Tol= 0.02
Split Flow Ratio= 0.02
Log Output Level= 0
Friction Slope Method= 1
Unsteady Friction Slope Method= 2
Unsteady Bridges Friction Slope Method= 1
Parabolic Critical Depth
Global Vel Dist=  1 , 1 , 1
Global Log Level= 0
CheckData=True
Encroach Param= -1, 0, 0, 0
BEGIN DESCRIPTION:
Multiple Run
END DESCRIPTION:

--- Stream0399.f01 (steady flow) ---

Flow Title=Multiple
Number of Profiles=7
Profile Names=10-year,25-year,50-year,1pct_min,100-year,1pct_plu,500-year
River Rch & RM= Stream0399,Reach-1,1728
     346     548     727     469     935    1866    1523
Boundary for River Rch & Prof#=Stream0399,Reach-1,1
Up Type=0
Dn Type=3
Dn Slope=0.005
Boundary for River Rch & Prof#=Stream0399,Reach-1,2
Up Type=0
Dn Type=3
Dn Slope=0.005
Boundary for River Rch & Prof#=Stream0399,Reach-1,3
Up Type=0
Dn Type=3
Dn Slope=0.005
Boundary for River Rch & Prof#=Stream0399,Reach-1,4
Up Type=0
Dn Type=3
Dn Slope=0.005
Boundary for River Rch & Prof#=Stream0399,Reach-1,5
Up Type=0
Dn Type=3
Dn Slope=0.005
Boundary for River Rch & Prof#=Stream0399,Reach-1,6
Up Type=0
Dn Type=3
Dn Slope=0.005
Boundary for River Rch & Prof#=Stream0399,Reach-1,7
Up Type=0
Dn Type=3
Dn Slope=0.005

--- Stream0399.g01 (geometry) ---

Geom Title=Existing Conditions

River Reach=Stream0399,Reach-1
Reach XY= 30
      1857925.00     13984025.00      1858151.47     13983797.86
      1858172.55     13983780.47      1858194.99     13983774.98
      1858300.11     13983775.27      1858323.53     13983771.45
      1858341.75     13983758.54      1858418.95     13983683.16
      1858431.04     13983677.50      1858477.17     13983668.86
      1858526.56     13983628.76      1858549.92     13983624.81
      1858669.07     13983622.70      1858681.07     13983616.81
      1858731.14     13983576.86      1858754.87     13983574.83
      1858773.37     13983578.62      1858815.13     13983613.61
      1858825.09     13983617.65      1858831.73     13983615.85
      1858972.55     13983480.46      1858999.88     13983474.71
      1859145.18     13983475.43      1859173.53     13983471.45
      1859191.75     13983458.54      1859268.96     13983383.17
      1859285.64     13983376.54      1859318.96     13983372.48
      1859334.70     13983364.28      1859425.00     13983275.00

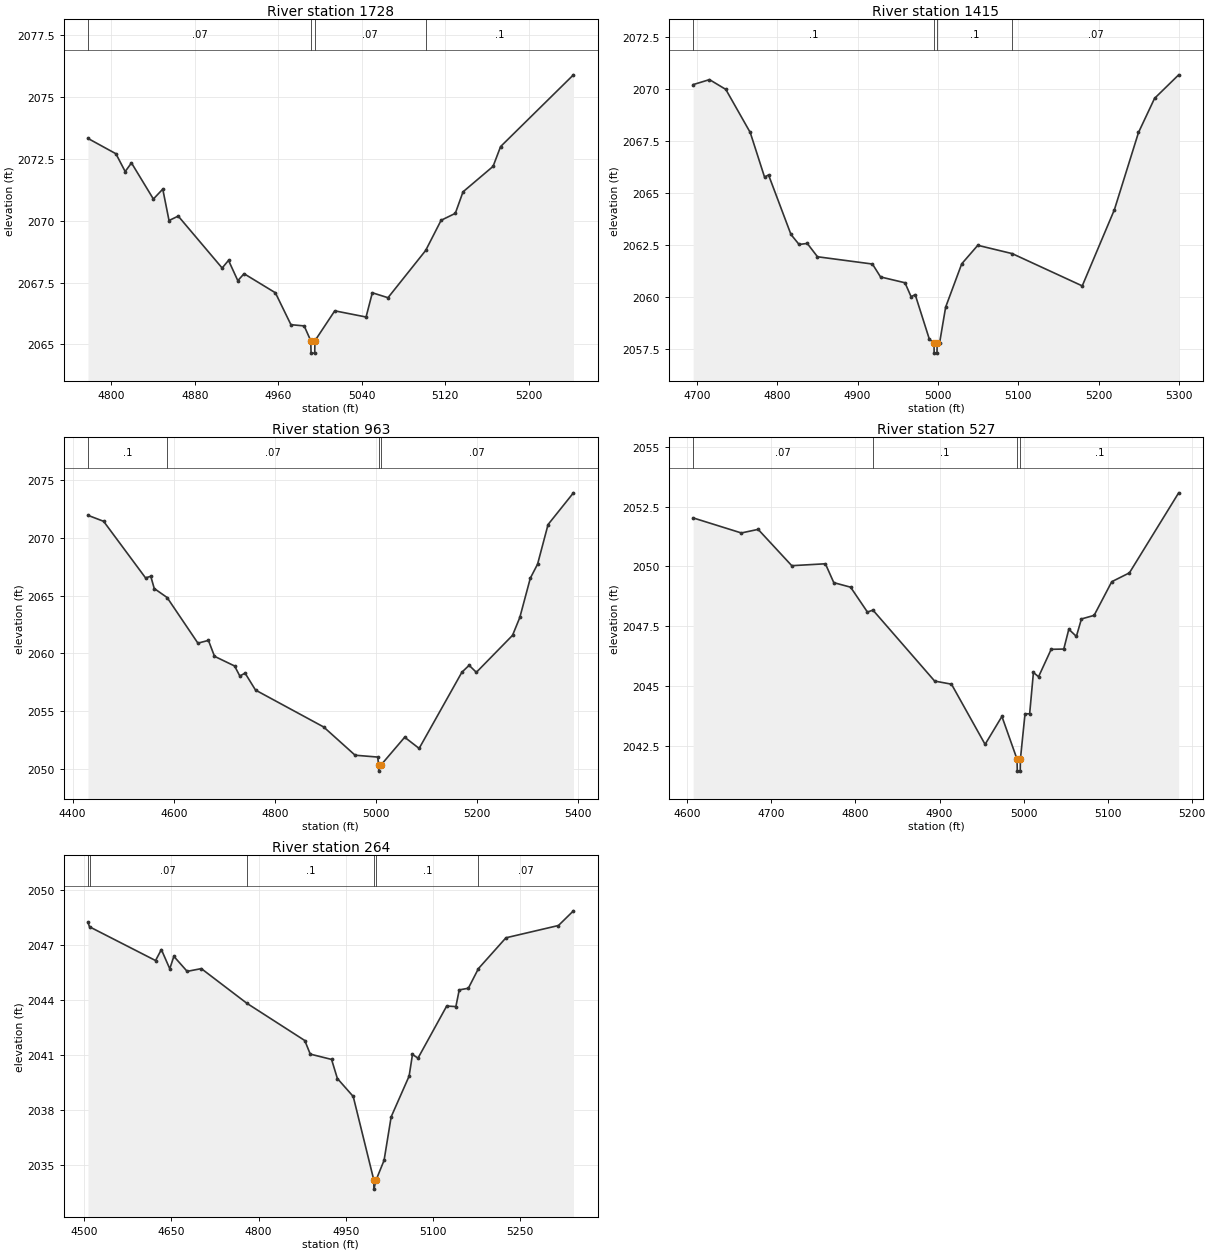
Type RM Length L Ch R = 1,1728,313,313,313
BEGIN DESCRIPTION:
Stream0399 4.0
END DESCRIPTION:
XS GIS Cut Line= 2
      1858111.98     13984146.65      1857851.54     13983761.19
#Sta/Elev= 30
  4777.7 2073.33  4804.5 2072.71  4813.4 2071.99  4819.4 2072.34  4840.4 2070.88
  4849.4 2071.28  4855.4 2070.01  4864.2 2070.19  4906.3 2068.09  4912.4 2068.40
  4921.3 2067.58  4927.3 2067.86  4957.3 2067.09  4972.2 2065.80  4984.9 2065.75
  4991.2 2065.15  4991.5 2064.65  4995.0 2064.65  4995.2 2065.15  5014.2 2066.36
  5044.2 2066.11  5050.2 2067.09  5065.2 2066.89  5101.3 2068.80  5116.1 2070.02
  5129.7 2070.30  5137.1 2071.17  5165.9 2072.20  5173.1 2073.00  5242.9 2075.90
#Mann=4,-1,0
  4777.7    0.07       0  4991.2    0.05       0  4995.2    0.07       0
  5101.3     0.1       0
Bank Sta=4991.2,4995.2
Exp/Cntr=0.3,0.1

Type RM Length L Ch R = 1,1415,452,452,452
BEGIN DESCRIPTION:
Stream0399 3.0
END DESCRIPTION:
XS GIS Cut Line= 3
      1858174.99     13984075.05      1858225.00     13983775.00
      1858225.00     13983474.99
#Sta/Elev= 30
  4695.5 2070.22  4715.8 2070.46  4736.1 2069.99  4766.5 2067.92  4784.3 2065.78
  4789.3 2065.88  4817.2 2063.02  4827.3 2062.54  4837.5 2062.59  4850.2 2061.95
  4918.6 2061.60  4928.7 2060.98  4959.1 2060.70  4966.7 2060.03  4971.8 2060.13
  4989.5 2057.98  4995.2 2057.82  4995.4 2057.32  4998.9 2057.32  4999.2 2057.82
  5002.2 2057.82  5009.7 2059.53  5029.7 2061.61  5049.7 2062.50  5092.6 2062.10
  5179.7 2060.55  5219.7 2064.21  5249.7 2067.92  5269.7 2069.56  5299.7 2070.69
#Mann=4,-1,0
  4695.5     0.1       0  4995.2    0.05       0  4999.2     0.1       0
  5092.6    0.07       0
Bank Sta=4995.2,4999.2
Exp/Cntr=0.3,0.1

Type RM Length L Ch R = 1,963,436,436,436
BEGIN DESCRIPTION:
Stream0399 2.0
END DESCRIPTION:
XS GIS Cut Line= 3
      1858475.01     13984174.95      1858625.00     13983625.00
      1858374.97     13983324.96
#Sta/Elev= 30
  4430.3 2071.97  4461.3 2071.45  4544.3 2066.54  4554.6 2066.68  4561.5 2065.62
  4586.9 2064.84  4647.9 2060.88  4668.7 2061.12  4680.7 2059.74  4720.5 2058.90
  4730.8 2058.03  4741.2 2058.28  4761.9 2056.81  4896.7 2053.61  4958.9 2051.16
  5003.6 2051.00  5005.5 2050.28  5005.7 2049.78  5009.5 2050.28  5057.0 2052.72
  5085.6 2051.75  5170.2 2058.36  5184.5 2058.96  5198.8 2058.35  5270.4 2061.56
  5284.8 2063.11  5305.6 2066.52  5319.9 2067.73  5340.7 2071.17  5390.9 2073.92
#Mann=4,-1,0
  4430.3     0.1       0  4586.9    0.07       0  5005.5    0.05       0
  5009.5    0.07       0
Bank Sta=5005.5,5009.5
Exp/Cntr=0.3,0.1

Type RM Length L Ch R = 1,527,263,263,263
BEGIN DESCRIPTION:
Stream0399 1.0
END DESCRIPTION:
XS GIS Cut Line= 3
      1858980.03     13983872.30      1858975.00     13983475.00
      1858875.00     13983325.01
#Sta/Elev= 30
  4606.9 2052.03  4664.2 2051.40  4684.2 2051.55  4724.2 2050.03  4764.2 2050.11
  4774.2 2049.32  4794.2 2049.13  4814.2 2048.09  4820.8 2048.17  4894.2 2045.20
  4914.2 2045.07  4954.2 2042.55  4974.2 2043.72  4992.2 2041.93  4992.5 2041.43
  4996.0 2041.43  4996.2 2041.93  5001.7 2043.83  5007.2 2043.83  5011.7 2045.56
  5017.8 2045.38  5032.8 2046.53  5047.8 2046.54  5053.8 2047.37  5062.8 2047.07
  5068.8 2047.80  5083.9 2047.95  5104.9 2049.36  5125.9 2049.73  5184.5 2053.08
#Mann=4,-1,0
  4606.9    0.07       0  4820.8     0.1       0  4992.2    0.05       0
  4996.2     0.1       0
Bank Sta=4992.2,4996.2
Exp/Cntr=0.3,0.1

Type RM Length L Ch R = 1,264,0,0,0
BEGIN DESCRIPTION:
Stream0399 0.0
END DESCRIPTION:
XS GIS Cut Line= 3
      1859129.33     13983882.77      1859271.70     13983518.17
      1859049.73     13983133.19
#Sta/Elev= 30
  4506.3 2048.24  4509.0 2048.00  4622.7 2046.16  4632.7 2046.76  4647.2 2045.71
  4654.2 2046.39  4677.1 2045.57  4701.5 2045.72  4779.9 2043.83  4879.6 2041.80
  4889.0 2041.06  4925.7 2040.77  4935.7 2039.73  4963.0 2038.75  4998.4 2034.20
  4998.6 2033.70  5002.4 2034.20  5016.1 2035.27  5028.3 2037.64  5059.2 2039.86
  5065.0 2041.04  5074.5 2040.84  5123.9 2043.68  5139.7 2043.65  5145.5 2044.56
  5161.2 2044.65  5178.5 2045.72  5225.9 2047.40  5316.3 2048.07  5342.1 2048.87
#Mann=6,-1,0
  4506.3     0.1       0  4509.0    0.07       0  4779.9     0.1       0
  4998.4    0.05       0  5002.4     0.1       0  5178.5    0.07       0
Bank Sta=4998.4,5002.4
Exp/Cntr=0.3,0.1

Chan Stop Cuts=-1