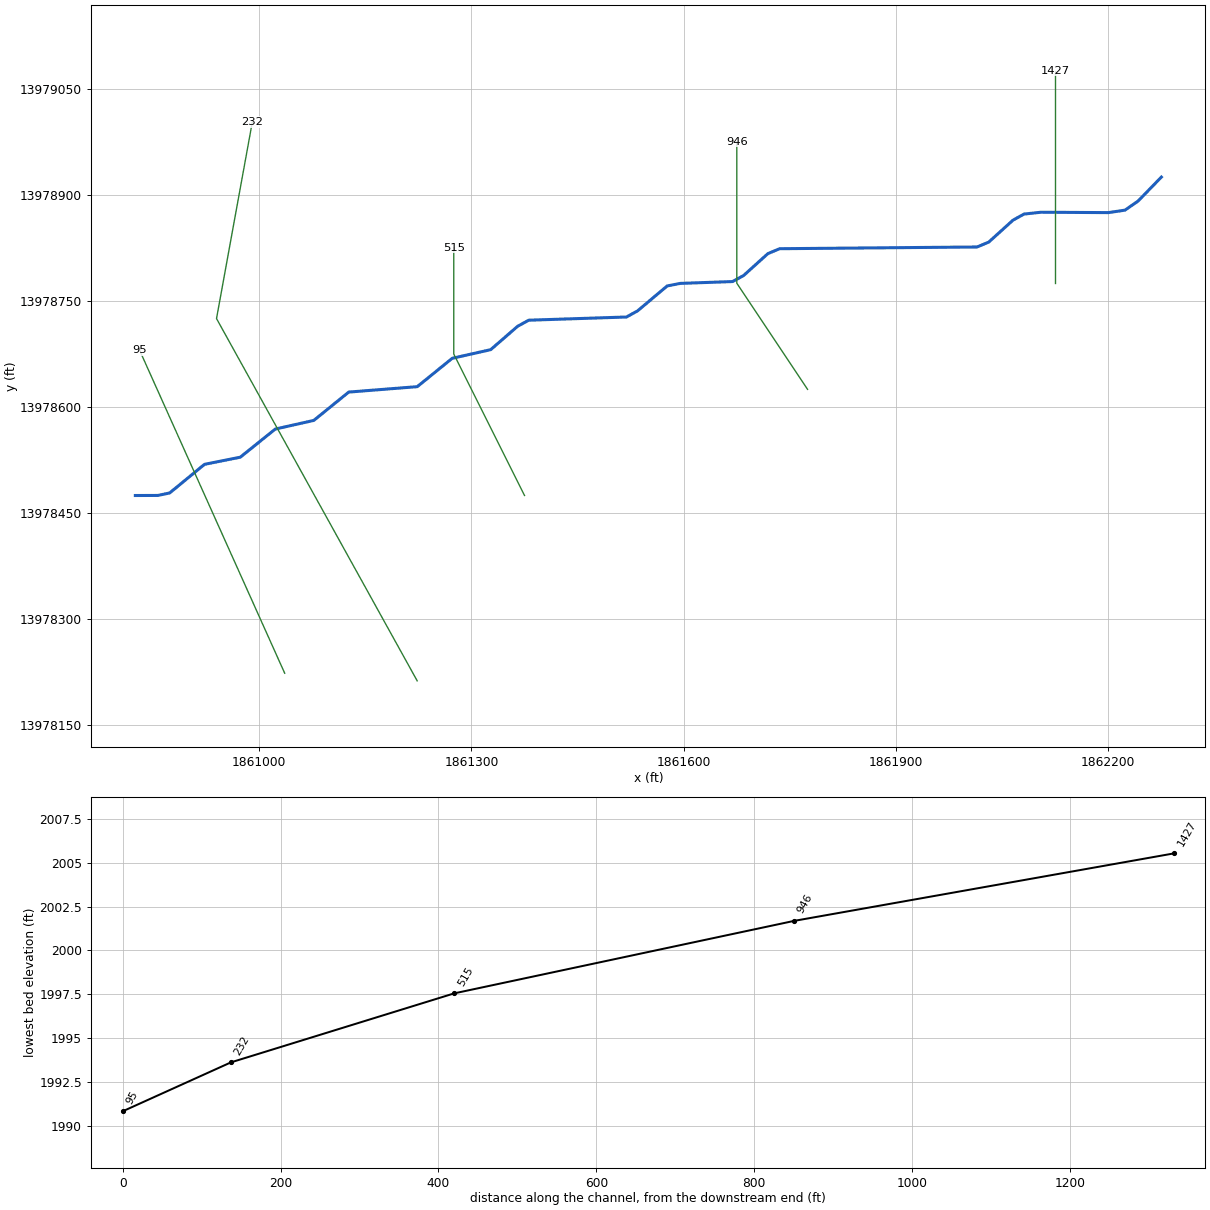
--- Stream0400.prj (project) ---

Proj Title=Stream0400 Base Level Engineering
Current Plan=p01
Default Exp/Contr=0.3,0.1
English Units
Geom File=g01
Flow File=f01
Plan File=p01
BEGIN DESCRIPTION:
Stream0400
END DESCRIPTION:

--- Stream0400.p01 (plan) ---

Plan Title=Multiple Run
Short Identifier=Multiple
Geom File=g01
Flow File=f01
Subcritical Flow
K Sum by GR= 0
Std Step Tol= 0.01
Critical Tol= 0.01
Num of Std Step Trials= 20
Max Error Tol= 0.3
Flow Tol Ratio= 0.001
Split Flow NTrial= 30
Split Flow Tol= 0.02
Split Flow Ratio= 0.02
Log Output Level= 0
Friction Slope Method= 1
Unsteady Friction Slope Method= 2
Unsteady Bridges Friction Slope Method= 1
Parabolic Critical Depth
Global Vel Dist=  1 , 1 , 1
Global Log Level= 0
CheckData=True
Encroach Param= -1, 0, 0, 0
BEGIN DESCRIPTION:
Multiple Run
END DESCRIPTION:

--- Stream0400.f01 (steady flow) ---

Flow Title=Multiple
Number of Profiles=7
Profile Names=10-year,25-year,50-year,1pct_min,100-year,1pct_plu,500-year
River Rch & RM= Stream0400,Reach-1,1427
    1257    2148    2998    2019    4029    8040    7194
Boundary for River Rch & Prof#=Stream0400,Reach-1,1
Up Type=0
Dn Type=3
Dn Slope=0.005
Boundary for River Rch & Prof#=Stream0400,Reach-1,2
Up Type=0
Dn Type=3
Dn Slope=0.005
Boundary for River Rch & Prof#=Stream0400,Reach-1,3
Up Type=0
Dn Type=3
Dn Slope=0.005
Boundary for River Rch & Prof#=Stream0400,Reach-1,4
Up Type=0
Dn Type=3
Dn Slope=0.005
Boundary for River Rch & Prof#=Stream0400,Reach-1,5
Up Type=0
Dn Type=3
Dn Slope=0.005
Boundary for River Rch & Prof#=Stream0400,Reach-1,6
Up Type=0
Dn Type=3
Dn Slope=0.005
Boundary for River Rch & Prof#=Stream0400,Reach-1,7
Up Type=0
Dn Type=3
Dn Slope=0.005

--- Stream0400.g01 (geometry) ---

Geom Title=Existing Conditions

River Reach=Stream0400,Reach-1
Reach XY= 30
      1862275.00     13978925.00      1862242.06     13978891.09
      1862223.63     13978878.30      1862200.09     13978874.79
      1862104.86     13978875.33      1862080.94     13978872.73
      1862065.35     13978864.14      1862031.06     13978833.14
      1862014.50     13978826.22      1861735.50     13978823.78
      1861718.94     13978816.86      1861684.63     13978785.89
      1861669.02     13978777.36      1861595.10     13978774.76
      1861576.60     13978771.14      1861534.65     13978735.85
      1861519.06     13978727.27      1861380.93     13978722.75
      1861365.33     13978714.20      1861327.18     13978681.12
      1861272.82     13978668.89      1861223.42     13978628.83
      1861126.58     13978621.17      1861077.18     13978581.12
      1861022.80     13978568.92      1860973.28     13978529.14
      1860922.75     13978519.05      1860873.51     13978478.60
      1860856.81     13978475.10      1860825.00     13978475.00

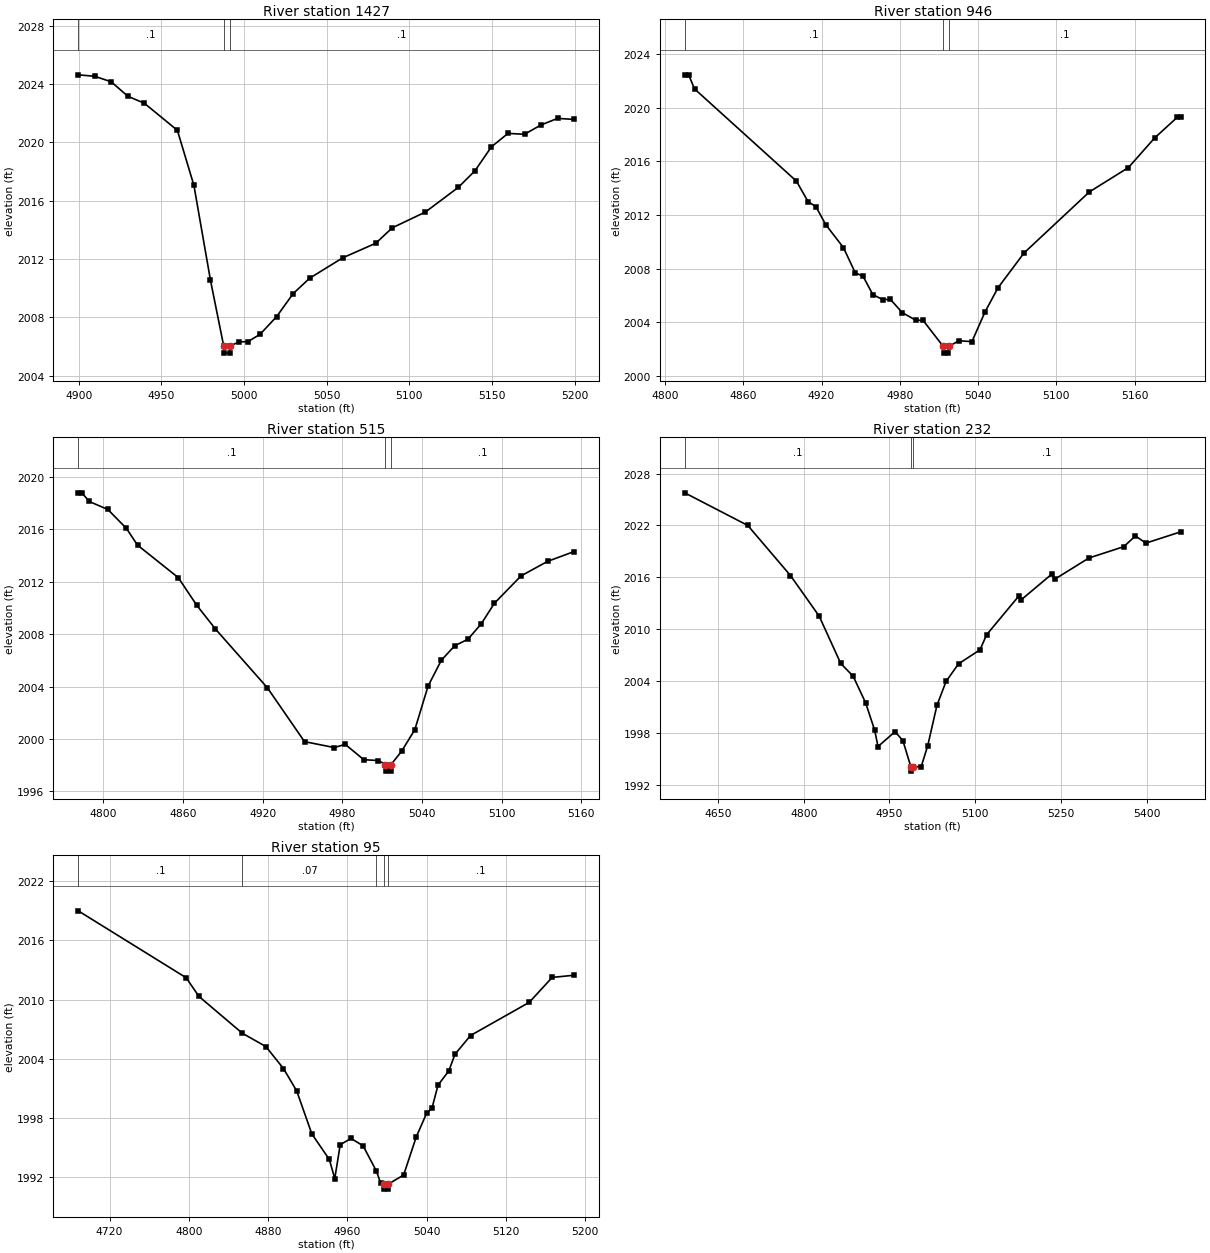
Type RM Length L Ch R = 1,1427,481,481,481
BEGIN DESCRIPTION:
Stream0400 3.0
END DESCRIPTION:
XS GIS Cut Line= 3
      1862125.00     13978775.05      1862125.00     13978875.00
      1862125.00     13979075.05
#Sta/Elev= 30
  4899.7 2024.64  4909.7 2024.54  4919.7 2024.16  4929.7 2023.17  4939.7 2022.69
  4959.7 2020.83  4969.7 2017.05  4979.7 2010.55  4987.7 2006.04  4987.9 2005.54
  4991.4 2005.54  4991.7 2006.04  4997.2 2006.32  5002.2 2006.32  5009.7 2006.83
  5019.7 2008.04  5029.7 2009.62  5039.7 2010.68  5059.7 2012.08  5079.7 2013.08
  5089.7 2014.14  5109.7 2015.22  5129.7 2016.92  5139.7 2018.05  5149.7 2019.70
  5159.7 2020.62  5169.7 2020.56  5179.7 2021.20  5189.7 2021.65  5199.7 2021.58
#Mann=3,-1,0
  4899.7     0.1       0  4987.7    0.05       0  4991.7     0.1       0
Bank Sta=4987.7,4991.7
Exp/Cntr=0.3,0.1

Type RM Length L Ch R = 1,946,431,431,431
BEGIN DESCRIPTION:
Stream0400 2.0
END DESCRIPTION:
XS GIS Cut Line= 3
      1861774.98     13978625.03      1861675.00     13978775.00
      1861675.00     13978974.96
#Sta/Elev= 30
  4815.1 2022.46  4818.1 2022.46  4822.6 2021.41  4900.7 2014.53  4909.7 2012.99
  4915.7 2012.62  4923.2 2011.28  4936.8 2009.56  4945.8 2007.69  4951.8 2007.43
  4959.3 2006.06  4966.8 2005.69  4972.8 2005.70  4981.8 2004.72  4992.3 2004.14
  4997.8 2004.14  5013.3 2002.19  5013.5 2001.69  5017.1 2001.69  5017.4 2002.19
  5025.3 2002.61  5035.3 2002.55  5045.3 2004.76  5055.3 2006.57  5075.3 2009.17
  5125.3 2013.72  5155.3 2015.54  5175.3 2017.74  5192.8 2019.30  5195.3 2019.30
#Mann=3,-1,0
  4815.1     0.1       0  5013.3    0.05       0  5017.4     0.1       0
Bank Sta=5013.3,5017.4
Exp/Cntr=0.3,0.1

Type RM Length L Ch R = 1,515,283,283,283
BEGIN DESCRIPTION:
Stream0400 1.0
END DESCRIPTION:
XS GIS Cut Line= 3
      1861374.98     13978475.04      1861275.00     13978675.00
      1861275.00     13978825.04
#Sta/Elev= 30
  4781.0 2018.78  4783.8 2018.78  4789.3 2018.12  4803.3 2017.51  4817.3 2016.07
  4825.7 2014.79  4856.4 2012.31  4870.4 2010.19  4884.4 2008.39  4923.5 2003.91
  4951.5 1999.80  4973.8 1999.35  4982.2 1999.59  4996.2 1998.42  5007.1 1998.36
  5012.5 1998.05  5012.8 1997.55  5016.4 1997.55  5016.7 1998.05  5024.6 1999.06
  5034.6 2000.71  5044.6 2004.04  5054.6 2006.01  5064.6 2007.11  5074.6 2007.61
  5084.6 2008.78  5094.6 2010.36  5114.6 2012.44  5134.6 2013.55  5154.6 2014.30
#Mann=3,-1,0
  4781.0     0.1       0  5012.5    0.05       0  5016.7     0.1       0
Bank Sta=5012.5,5016.7
Exp/Cntr=0.3,0.1

Type RM Length L Ch R = 1,232,137,137,137
BEGIN DESCRIPTION:
Stream0400 0.0
END DESCRIPTION:
XS GIS Cut Line= 3
      1861223.27     13978213.15      1860939.71     13978725.06
      1860990.32     13979002.79
#Sta/Elev= 30
  4591.8 2025.77  4702.1 2022.00  4776.8 2016.21  4826.9 2011.53  4864.7 2006.05
  4886.4 2004.58  4908.2 2001.51  4924.2 1998.31  4929.9 1996.45  4959.7 1998.17
  4973.4 1997.14  4987.4 1994.11  4987.6 1993.61  4991.6 1994.11  5005.5 1994.14
  5016.9 1996.55  5033.0 2001.21  5049.0 2003.98  5070.8 2006.01  5108.3 2007.63
  5120.0 2009.38  5176.7 2013.88  5180.3 2013.40  5233.6 2016.36  5238.7 2015.77
  5298.9 2018.24  5359.9 2019.55  5380.2 2020.79  5398.6 2019.96  5459.3 2021.26
#Mann=3,-1,0
  4591.8     0.1       0  4987.4    0.05       0  4991.6     0.1       0
Bank Sta=4987.4,4991.6
Exp/Cntr=0.3,0.1

Type RM Length L Ch R = 1,95,0,0,0
BEGIN DESCRIPTION:
Strea0400 0.1
END DESCRIPTION:
XS GIS Cut Line= 2
      1861036.08     13978223.83      1860831.01     13978680.28
#Sta/Elev= 30
  4688.3 2018.99  4797.2 2012.22  4810.2 2010.32  4853.9 2006.60  4877.7 2005.25
  4895.4 2003.03  4908.8 2000.76  4924.0 1996.42  4941.7 1993.82  4947.2 1991.89
  4952.7 1995.32  4963.7 1995.95  4975.8 1995.20  4989.2 1992.65  4993.5 1991.43
  4996.9 1991.32  4997.1 1990.82  5000.8 1990.82  5001.1 1991.32  5016.7 1992.25
  5029.4 1996.10  5039.8 1998.48  5045.3 1999.02  5051.4 2001.35  5062.3 2002.79
  5068.5 2004.47  5084.2 2006.37  5143.4 2009.72  5166.6 2012.25  5188.7 2012.47
#Mann=5,-1,0
  4688.3     0.1       0  4853.9    0.07       0  4989.2     0.1       0
  4996.9    0.05       0  5001.1     0.1       0
Bank Sta=4996.9,5001.1
Exp/Cntr=0.3,0.1

Chan Stop Cuts=-1