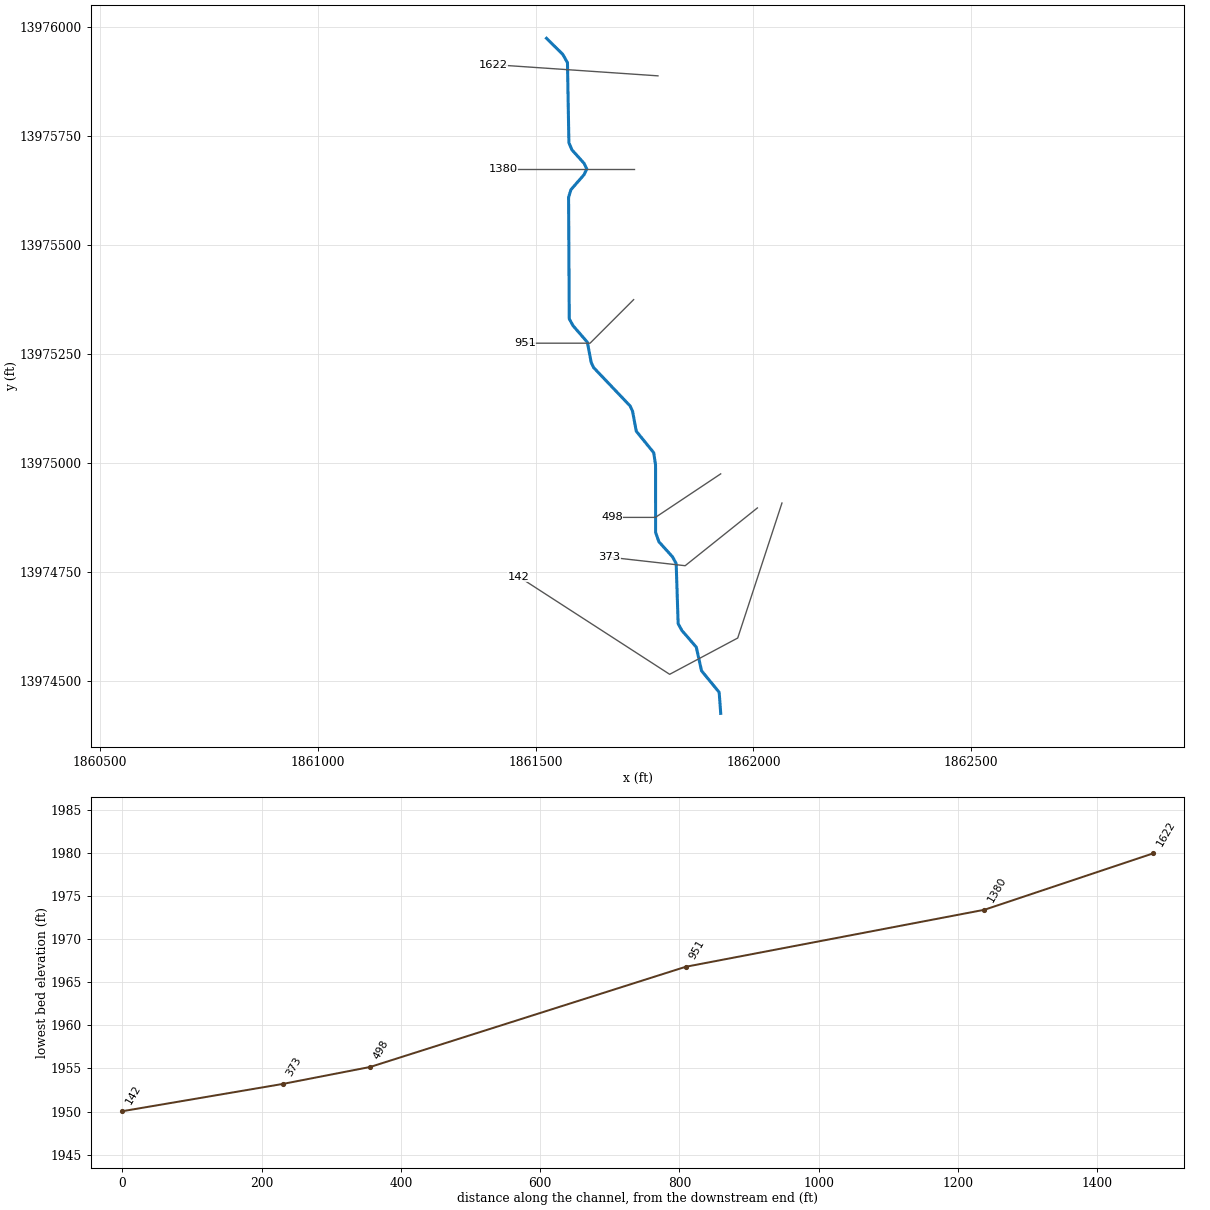
--- Stream0401.prj (project) ---

Proj Title=Stream0401 Base Level Engineering
Current Plan=p01
Default Exp/Contr=0.3,0.1
English Units
Geom File=g01
Flow File=f01
Plan File=p01
BEGIN DESCRIPTION:
Stream0401
END DESCRIPTION:

--- Stream0401.p01 (plan) ---

Plan Title=Multiple Run
Short Identifier=Multiple
Geom File=g01
Flow File=f01
Subcritical Flow
K Sum by GR= 0
Std Step Tol= 0.01
Critical Tol= 0.01
Num of Std Step Trials= 20
Max Error Tol= 0.3
Flow Tol Ratio= 0.001
Split Flow NTrial= 30
Split Flow Tol= 0.02
Split Flow Ratio= 0.02
Log Output Level= 0
Friction Slope Method= 1
Unsteady Friction Slope Method= 2
Unsteady Bridges Friction Slope Method= 1
Parabolic Critical Depth
Global Vel Dist=  1 , 1 , 1
Global Log Level= 0
CheckData=True
Encroach Param= -1, 0, 0, 0
BEGIN DESCRIPTION:
Multiple Run
END DESCRIPTION:

--- Stream0401.f01 (steady flow) ---

Flow Title=Multiple
Number of Profiles=7
Profile Names=10-year,25-year,50-year,1pct_min,100-year,1pct_plu,500-year
River Rch & RM= Stream0401,Reach-1,1622
     382     606     804     518    1035    2064    1685
Boundary for River Rch & Prof#=Stream0401,Reach-1,1
Up Type=0
Dn Type=3
Dn Slope=0.005
Boundary for River Rch & Prof#=Stream0401,Reach-1,2
Up Type=0
Dn Type=3
Dn Slope=0.005
Boundary for River Rch & Prof#=Stream0401,Reach-1,3
Up Type=0
Dn Type=3
Dn Slope=0.005
Boundary for River Rch & Prof#=Stream0401,Reach-1,4
Up Type=0
Dn Type=3
Dn Slope=0.005
Boundary for River Rch & Prof#=Stream0401,Reach-1,5
Up Type=0
Dn Type=3
Dn Slope=0.005
Boundary for River Rch & Prof#=Stream0401,Reach-1,6
Up Type=0
Dn Type=3
Dn Slope=0.005
Boundary for River Rch & Prof#=Stream0401,Reach-1,7
Up Type=0
Dn Type=3
Dn Slope=0.005

--- Stream0401.g01 (geometry) ---

Geom Title=Existing Conditions

River Reach=Stream0401,Reach-1
Reach XY= 30
      1861525.00     13975975.00      1861562.08     13975938.50
      1861573.11     13975919.22      1861576.38     13975735.44
      1861583.45     13975718.81      1861611.05     13975688.21
      1861617.44     13975675.00      1861611.05     13975661.79
      1861581.02     13975627.45      1861575.66     13975609.84
      1861577.24     13975330.93      1861585.79     13975315.33
      1861618.86     13975277.17      1861627.50     13975231.04
      1861633.16     13975218.95      1861716.84     13975131.05
      1861722.50     13975118.96      1861731.14     13975072.83
      1861771.25     13975023.45      1861775.36     13974995.15
      1861775.52     13974840.22      1861783.14     13974818.94
      1861814.14     13974784.64      1861822.73     13974769.06
      1861827.25     13974630.93      1861835.80     13974615.33
      1861868.89     13974577.19      1861880.95     13974522.75
      1861921.40     13974473.51      1861925.00     13974425.00

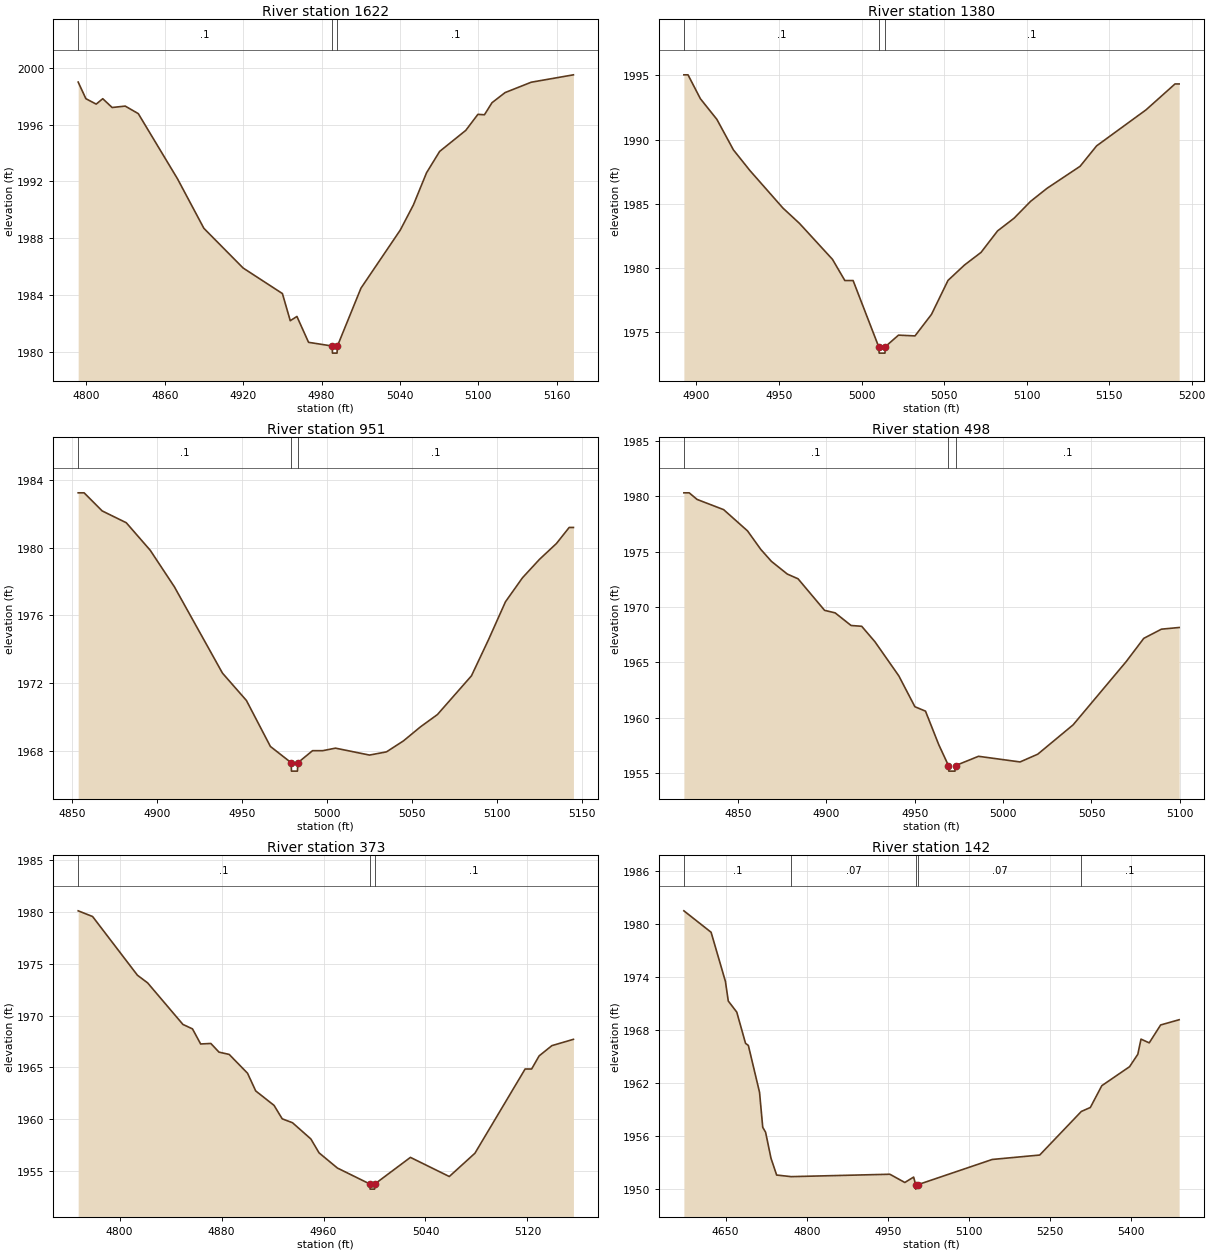
Type RM Length L Ch R = 1,1622,242,242,242
BEGIN DESCRIPTION:
Stream0401 4.0
END DESCRIPTION:
XS GIS Cut Line= 2
      1861780.93     13975888.87      1861402.81     13975914.69
#Sta/Elev= 30
  4793.7 1998.99  4799.6 1997.82  4807.5 1997.44  4812.5 1997.82  4819.7 1997.20
  4829.7 1997.30  4839.7 1996.77  4869.8 1992.17  4889.9 1988.70  4919.9 1985.91
  4950.0 1984.11  4956.0 1982.20  4961.1 1982.50  4970.0 1980.68  4988.1 1980.42
  4988.3 1979.92  4991.8 1979.92  4992.1 1980.42  5010.1 1984.49  5040.2 1988.58
  5050.2 1990.34  5060.3 1992.61  5070.3 1994.11  5090.3 1995.59  5099.6 1996.72
  5104.6 1996.69  5110.4 1997.54  5120.4 1998.25  5140.4 1998.98  5172.7 1999.50
#Mann=3,-1,0
  4793.7     0.1       0  4988.1    0.05       0  4992.1     0.1       0
Bank Sta=4988.1,4992.1
Exp/Cntr=0.3,0.1

Type RM Length L Ch R = 1,1380,429,429,429
BEGIN DESCRIPTION:
Stream0401 3.0
END DESCRIPTION:
XS GIS Cut Line= 3
      1861725.04     13975675.00      1861625.00     13975675.00
      1861425.04     13975675.00
#Sta/Elev= 30
  4892.4 1995.05  4894.9 1995.05  4902.4 1993.19  4912.4 1991.58  4922.4 1989.21
  4932.4 1987.60  4952.4 1984.68  4962.4 1983.49  4982.4 1980.69  4989.9 1979.04
  4994.9 1979.04  5010.4 1973.89  5010.7 1973.39  5014.2 1973.39  5014.4 1973.89
  5022.4 1974.79  5032.4 1974.73  5042.4 1976.41  5052.4 1979.05  5062.4 1980.25
  5072.4 1981.23  5082.4 1982.90  5092.4 1983.89  5102.4 1985.20  5112.4 1986.22
  5132.4 1987.93  5142.4 1989.52  5172.4 1992.33  5189.9 1994.34  5192.4 1994.34
#Mann=3,-1,0
  4892.4     0.1       0  5010.4    0.05       0  5014.4     0.1       0
Bank Sta=5010.4,5014.4
Exp/Cntr=0.3,0.1

Type RM Length L Ch R = 1,951,453,453,453
BEGIN DESCRIPTION:
Stream0401 2.0
END DESCRIPTION:
XS GIS Cut Line= 3
      1861725.00     13975375.00      1861625.00     13975275.00
      1861475.02     13975275.00
#Sta/Elev= 29
  4853.5 1983.25  4857.0 1983.25  4867.6 1982.18  4881.8 1981.48  4895.9 1979.85
  4910.1 1977.69  4938.4 1972.58  4952.5 1970.96  4966.6 1968.24  4978.8 1967.28
  4979.0 1966.78  4982.5 1966.78  4982.8 1967.28  4991.4 1967.99  4997.4 1967.99
  5004.9 1968.14  5024.9 1967.73  5034.9 1967.92  5044.9 1968.57  5054.9 1969.40
  5064.9 1970.13  5084.9 1972.42  5094.9 1974.55  5104.9 1976.80  5114.9 1978.22
  5124.9 1979.31  5134.9 1980.25  5142.4 1981.20  5144.9 1981.20
#Mann=3,-1,0
  4853.5     0.1       0  4978.8    0.05       0  4982.8     0.1       0
Bank Sta=4978.8,4982.8
Exp/Cntr=0.3,0.1

Type RM Length L Ch R = 1,498,125,125,125
BEGIN DESCRIPTION:
Stream0401 1.0
END DESCRIPTION:
XS GIS Cut Line= 3
      1861924.96     13974974.97      1861775.00     13974875.00
      1861675.03     13974875.00
#Sta/Elev= 30
  4819.4 1980.32  4822.4 1980.32  4826.9 1979.72  4841.9 1978.80  4855.4 1976.88
  4862.9 1975.21  4868.9 1974.13  4877.9 1972.98  4884.0 1972.55  4899.0 1969.70
  4905.0 1969.47  4914.0 1968.33  4920.0 1968.26  4927.5 1966.86  4941.0 1963.78
  4950.1 1960.99  4956.1 1960.59  4963.6 1957.56  4969.1 1955.67  4969.3 1955.17
  4972.8 1955.17  4973.1 1955.67  4986.1 1956.51  5009.6 1956.00  5019.6 1956.70
  5039.6 1959.35  5069.6 1965.06  5079.6 1967.17  5089.6 1968.00  5099.6 1968.15
#Mann=3,-1,0
  4819.4     0.1       0  4969.1    0.05       0  4973.1     0.1       0
Bank Sta=4969.1,4973.1
Exp/Cntr=0.3,0.1

Type RM Length L Ch R = 1,373,231,231,231
BEGIN DESCRIPTION:
Stream0401 0.0
END DESCRIPTION:
XS GIS Cut Line= 3
      1862009.19     13974896.73      1861843.35     13974764.07
      1861668.23     13974783.77
#Sta/Elev= 30
  4767.5 1980.13  4778.8 1979.58  4814.0 1973.90  4822.0 1973.16  4849.7 1969.14
  4857.2 1968.71  4863.6 1967.25  4871.6 1967.30  4878.0 1966.46  4886.0 1966.24
  4900.4 1964.42  4906.8 1962.71  4921.2 1961.31  4927.6 1960.01  4935.7 1959.63
  4950.1 1958.06  4956.5 1956.72  4970.9 1955.25  4996.3 1953.71  4996.6 1953.21
  5000.1 1953.21  5000.3 1953.71  5028.2 1956.28  5058.7 1954.43  5078.8 1956.68
  5118.2 1964.83  5123.3 1964.83  5129.2 1966.10  5139.2 1967.09  5156.1 1967.70
#Mann=3,-1,0
  4767.5     0.1       0  4996.3    0.05       0  5000.3     0.1       0
Bank Sta=4996.3,5000.3
Exp/Cntr=0.3,0.1

Type RM Length L Ch R = 1,142,0,0,0
BEGIN DESCRIPTION:
Stream0401 0.1
END DESCRIPTION:
XS GIS Cut Line= 4
      1862065.60     13974907.97      1861964.03     13974598.03
      1861807.78     13974514.70      1861461.41     13974738.66
#Sta/Elev= 30
  4572.9 1981.47  4623.2 1979.05  4649.7 1973.50  4655.0 1971.28  4670.7 1970.03
  4686.9 1966.50  4692.1 1966.27  4712.8 1960.97  4718.7 1957.02  4724.0 1956.46
  4733.9 1953.54  4744.4 1951.63  4771.2 1951.45  4953.8 1951.72  4981.4 1950.79
  4997.7 1951.40  5001.4 1950.54  5001.6 1950.04  5005.4 1950.54  5143.0 1953.39
  5230.8 1953.89  5307.7 1958.81  5324.4 1959.26  5345.6 1961.72  5397.0 1963.87
  5412.2 1965.27  5418.1 1966.98  5433.3 1966.56  5454.4 1968.58  5488.6 1969.17
#Mann=5,-1,0
  4572.9     0.1       0  4771.2    0.07       0  5001.4    0.05       0
  5005.4    0.07       0  5307.7     0.1       0
Bank Sta=5001.4,5005.4
Exp/Cntr=0.3,0.1

Chan Stop Cuts=-1