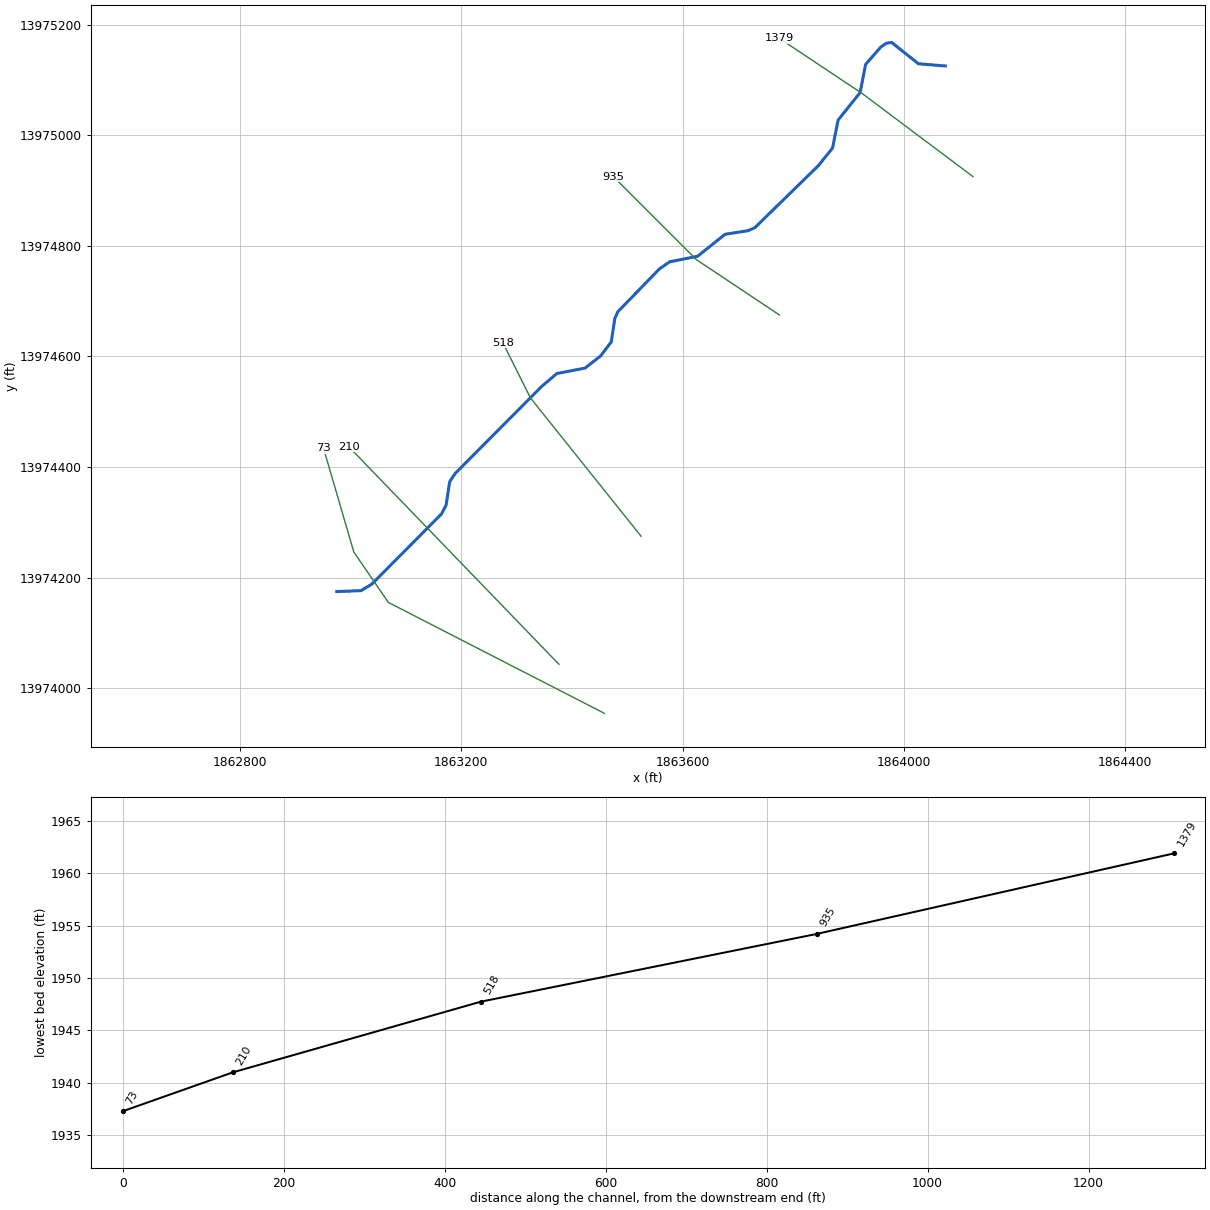
--- Stream0402.prj (project) ---

Proj Title=Stream0402 Base Level Engineering
Current Plan=p01
Default Exp/Contr=0.3,0.1
English Units
Geom File=g01
Flow File=f01
Plan File=p01
BEGIN DESCRIPTION:
Stream0402
END DESCRIPTION:

--- Stream0402.p01 (plan) ---

Plan Title=Multiple Run
Short Identifier=Multiple
Geom File=g01
Flow File=f01
Subcritical Flow
K Sum by GR= 0
Std Step Tol= 0.01
Critical Tol= 0.01
Num of Std Step Trials= 20
Max Error Tol= 0.3
Flow Tol Ratio= 0.001
Split Flow NTrial= 30
Split Flow Tol= 0.02
Split Flow Ratio= 0.02
Log Output Level= 0
Friction Slope Method= 1
Unsteady Friction Slope Method= 2
Unsteady Bridges Friction Slope Method= 1
Parabolic Critical Depth
Global Vel Dist=  1 , 1 , 1
Global Log Level= 0
CheckData=True
Encroach Param= -1, 0, 0, 0
BEGIN DESCRIPTION:
Multiple Run
END DESCRIPTION:

--- Stream0402.f01 (steady flow) ---

Flow Title=Multiple
Number of Profiles=7
Profile Names=10-year,25-year,50-year,1pct_min,100-year,1pct_plu,500-year
River Rch & RM= Stream0402,Reach-1,1379
     690    1145    1567    1039    2074    4138    3581
Boundary for River Rch & Prof#=Stream0402,Reach-1,1
Up Type=0
Dn Type=3
Dn Slope=0.005
Boundary for River Rch & Prof#=Stream0402,Reach-1,2
Up Type=0
Dn Type=3
Dn Slope=0.005
Boundary for River Rch & Prof#=Stream0402,Reach-1,3
Up Type=0
Dn Type=3
Dn Slope=0.005
Boundary for River Rch & Prof#=Stream0402,Reach-1,4
Up Type=0
Dn Type=3
Dn Slope=0.005
Boundary for River Rch & Prof#=Stream0402,Reach-1,5
Up Type=0
Dn Type=3
Dn Slope=0.005
Boundary for River Rch & Prof#=Stream0402,Reach-1,6
Up Type=0
Dn Type=3
Dn Slope=0.005
Boundary for River Rch & Prof#=Stream0402,Reach-1,7
Up Type=0
Dn Type=3
Dn Slope=0.005

--- Stream0402.g01 (geometry) ---

Geom Title=Existing Conditions

River Reach=Stream0402,Reach-1
Reach XY= 30
      1864075.00     13975125.00      1864026.34     13975129.03
      1863978.05     13975167.54      1863967.98     13975166.15
      1863957.91     13975158.92      1863930.82     13975127.85
      1863920.81     13975076.80      1863881.10     13975027.19
      1863871.05     13974976.63      1863845.39     13974944.84
      1863731.06     13974833.14      1863718.97     13974827.50
      1863676.74     13974820.81      1863627.19     13974781.10
      1863576.62     13974771.06      1863558.29     13974758.37
      1863483.16     13974681.05      1863477.55     13974668.92
      1863471.11     13974626.43      1863452.14     13974601.16
      1863423.57     13974578.89      1863372.73     13974569.13
      1863344.84     13974545.38      1863188.63     13974388.21
      1863178.98     13974373.35      1863172.47     13974331.05
      1863164.22     13974315.32      1863038.28     13974188.47
      1863018.86     13974176.68      1862975.00     13974175.00

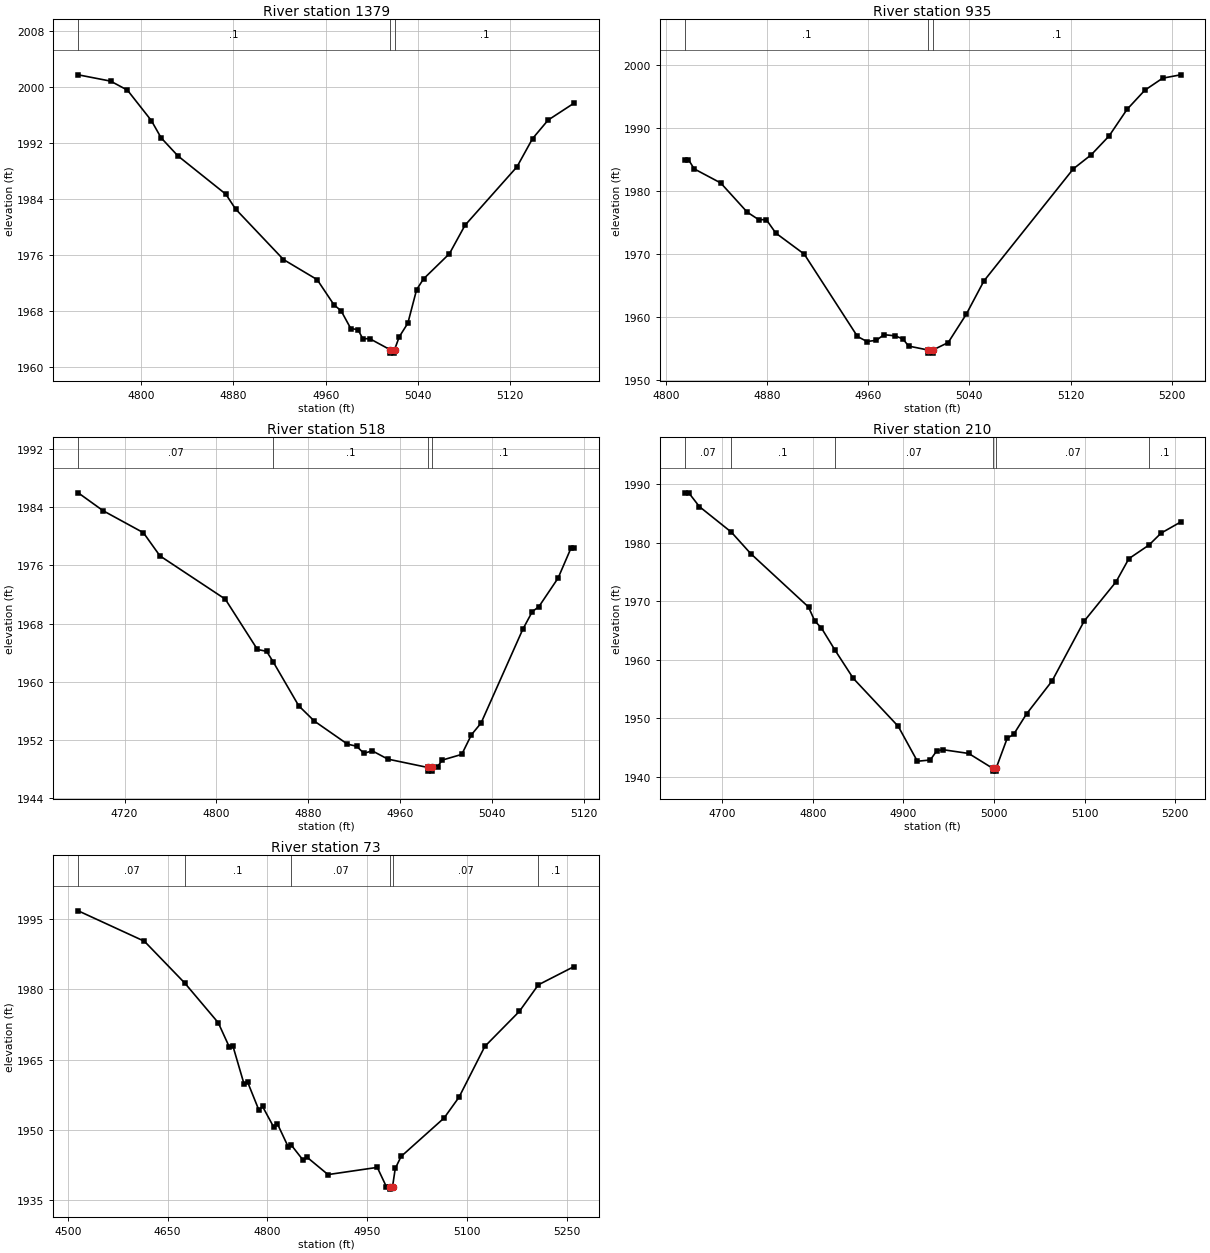
Type RM Length L Ch R = 1,1379,444,444,444
BEGIN DESCRIPTION:
Stream0402 3.0
END DESCRIPTION:
XS GIS Cut Line= 3
      1864125.00     13974925.00      1863925.00     13975075.00
      1863774.98     13975175.02
#Sta/Elev= 30
  4745.3 2001.71  4773.4 2000.81  4788.0 1999.52  4808.8 1995.16  4817.2 1992.71
  4831.8 1990.12  4873.4 1984.64  4881.8 1982.53  4923.4 1975.30  4952.6 1972.43
  4967.2 1968.83  4973.4 1967.97  4981.8 1965.43  4988.0 1965.29  4992.2 1963.98
  4998.3 1963.98  5015.8 1962.42  5016.1 1961.92  5019.6 1961.92  5019.8 1962.42
  5023.8 1964.24  5031.3 1966.20  5038.9 1970.99  5044.9 1972.53  5067.4 1976.14
  5080.9 1980.20  5126.0 1988.56  5139.5 1992.59  5153.0 1995.24  5175.6 1997.67
#Mann=3,-1,0
  4745.3     0.1       0  5015.8    0.05       0  5019.8     0.1       0
Bank Sta=5015.8,5019.8
Exp/Cntr=0.3,0.1

Type RM Length L Ch R = 1,935,417,417,417
BEGIN DESCRIPTION:
Stream0402 2.0
END DESCRIPTION:
XS GIS Cut Line= 3
      1863774.97     13974675.02      1863625.00     13974775.00
      1863474.99     13974925.01
#Sta/Elev= 30
  4814.7 1984.94  4817.7 1984.94  4822.2 1983.48  4843.2 1981.24  4864.2 1976.60
  4873.3 1975.41  4879.3 1975.41  4886.8 1973.28  4909.3 1969.94  4951.4 1956.87
  4958.9 1956.06  4966.4 1956.26  4972.4 1957.15  4981.4 1956.96  4987.4 1956.46
  4991.9 1955.34  5007.1 1954.72  5007.3 1954.22  5010.8 1954.22  5011.1 1954.72
  5023.2 1955.90  5037.4 1960.36  5051.5 1965.69  5122.2 1983.48  5136.4 1985.72
  5150.5 1988.70  5164.7 1992.92  5178.8 1995.97  5192.9 1997.88  5207.1 1998.41
#Mann=3,-1,0
  4814.7     0.1       0  5007.1    0.05       0  5011.1     0.1       0
Bank Sta=5007.1,5011.1
Exp/Cntr=0.3,0.1

Type RM Length L Ch R = 1,518,308,308,308
BEGIN DESCRIPTION:
Stream0402 1.0
END DESCRIPTION:
XS GIS Cut Line= 3
      1863525.01     13974274.99      1863325.00     13974525.00
      1863274.99     13974625.03
#Sta/Elev= 30
  4679.6 1985.97  4701.2 1983.52  4736.4 1980.49  4750.8 1977.31  4807.7 1971.37
  4835.7 1964.46  4843.7 1964.20  4849.3 1962.79  4871.7 1956.72  4885.3 1954.62
  4914.1 1951.46  4922.1 1951.17  4928.5 1950.19  4935.7 1950.54  4949.3 1949.40
  4984.2 1948.25  4984.4 1947.75  4987.9 1947.75  4988.2 1948.25  4992.6 1948.34
  4996.6 1949.26  5013.7 1950.05  5022.1 1952.74  5030.5 1954.35  5066.8 1967.21
  5075.2 1969.67  5080.8 1970.32  5097.6 1974.26  5108.8 1978.36  5111.6 1978.36
#Mann=4,-1,0
  4679.6    0.07       0  4849.3     0.1       0  4984.2    0.05       0
  4988.2     0.1       0
Bank Sta=4984.2,4988.2
Exp/Cntr=0.3,0.1

Type RM Length L Ch R = 1,210,137,137,137
BEGIN DESCRIPTION:
Stream0402 0.0
END DESCRIPTION:
XS GIS Cut Line= 2
      1863376.55     13974043.50      1862996.46     13974437.00
#Sta/Elev= 30
  4658.7 1988.55  4663.2 1988.55  4674.9 1986.20  4710.2 1981.83  4731.5 1978.17
  4795.3 1969.04  4802.2 1966.65  4809.4 1965.49  4824.5 1961.68  4844.7 1956.85
  4894.3 1948.65  4915.4 1942.69  4929.6 1942.90  4936.8 1944.47  4943.7 1944.66
  4972.0 1944.02  4998.3 1941.50  4998.6 1941.00  5002.1 1941.00  5002.3 1941.50
  5014.5 1946.62  5021.6 1947.28  5035.8 1950.77  5064.0 1956.41  5099.3 1966.61
  5134.6 1973.35  5148.7 1977.30  5170.9 1979.63  5184.2 1981.66  5205.8 1983.56
#Mann=6,-1,0
  4658.7    0.07       0  4710.2     0.1       0  4824.5    0.07       0
  4998.3    0.05       0  5002.3    0.07       0  5170.9     0.1       0
Bank Sta=4998.3,5002.3
Exp/Cntr=0.3,0.1

Type RM Length L Ch R = 1,73,0,0,0
BEGIN DESCRIPTION:
Stream0402 0.1
END DESCRIPTION:
XS GIS Cut Line= 4
      1863458.81     13973954.81      1863068.19     13974155.33
      1863005.69     13974246.47      1862951.01     13974433.97
#Sta/Elev= 30
  4515.8 1996.81  4615.2 1990.30  4675.9 1981.35  4726.1 1972.88  4742.7 1967.70
  4748.3 1967.83  4764.9 1959.75  4770.5 1960.09  4787.1 1954.21  4792.7 1954.96
  4809.3 1950.58  4814.9 1951.28  4831.5 1946.24  4835.5 1946.76  4853.7 1943.46
  4859.3 1944.13  4891.0 1940.39  4965.0 1941.93  4978.7 1937.78  4983.9 1937.78
  4984.2 1937.28  4987.9 1937.78  4992.0 1941.70  5000.8 1944.27  5065.4 1952.50
  5087.8 1956.95  5126.5 1967.80  5178.4 1975.30  5206.9 1980.98  5260.7 1984.90
#Mann=6,-1,0
  4515.8    0.07       0  4675.9     0.1       0  4835.5    0.07       0
  4983.9    0.05       0  4987.9    0.07       0  5206.9     0.1       0
Bank Sta=4983.9,4987.9
Exp/Cntr=0.3,0.1

Chan Stop Cuts=-1