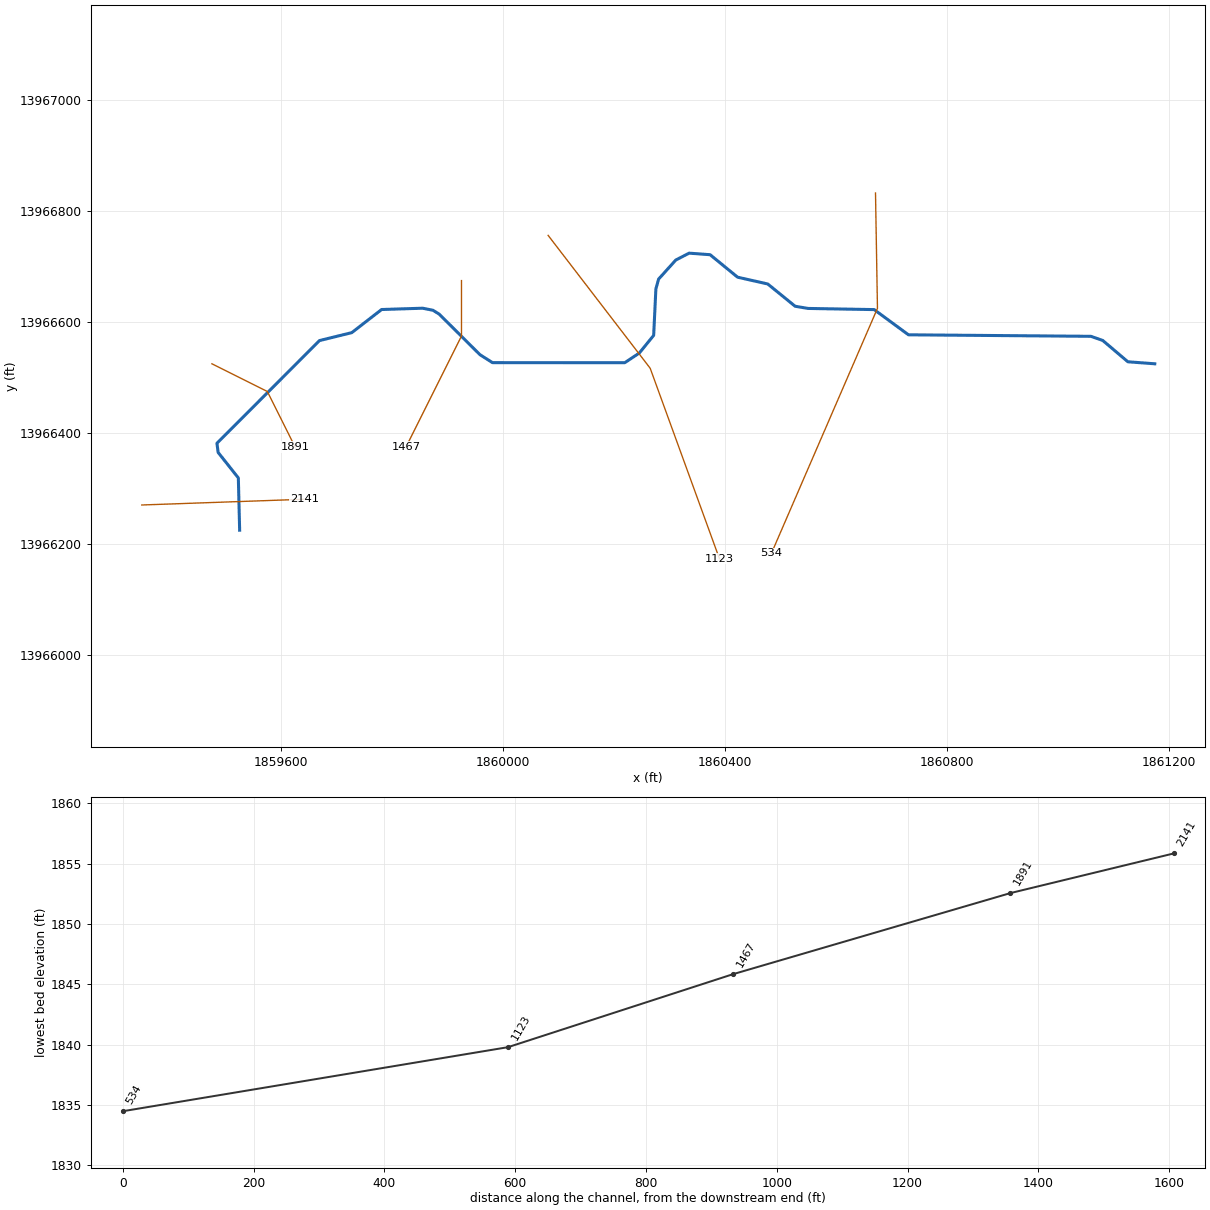
--- Stream0403.prj (project) ---

Proj Title=Stream0403 Base Level Engineering
Current Plan=p01
Default Exp/Contr=0.3,0.1
English Units
Geom File=g01
Flow File=f01
Plan File=p01
BEGIN DESCRIPTION:
Stream0403
END DESCRIPTION:

--- Stream0403.p01 (plan) ---

Plan Title=Multiple Run
Short Identifier=Multiple
Geom File=g01
Flow File=f01
Subcritical Flow
K Sum by GR= 0
Std Step Tol= 0.01
Critical Tol= 0.01
Num of Std Step Trials= 20
Max Error Tol= 0.3
Flow Tol Ratio= 0.001
Split Flow NTrial= 30
Split Flow Tol= 0.02
Split Flow Ratio= 0.02
Log Output Level= 0
Friction Slope Method= 1
Unsteady Friction Slope Method= 2
Unsteady Bridges Friction Slope Method= 1
Parabolic Critical Depth
Global Vel Dist=  1 , 1 , 1
Global Log Level= 0
CheckData=True
Encroach Param= -1, 0, 0, 0
BEGIN DESCRIPTION:
Multiple Run
END DESCRIPTION:

--- Stream0403.f01 (steady flow) ---

Flow Title=Multiple
Number of Profiles=7
Profile Names=10-year,25-year,50-year,1pct_min,100-year,1pct_plu,500-year
River Rch & RM= Stream0403,Reach-1,2141
     981    1658    2298    1539    3072    6129    5420
Boundary for River Rch & Prof#=Stream0403,Reach-1,1
Up Type=0
Dn Type=3
Dn Slope=0.005
Boundary for River Rch & Prof#=Stream0403,Reach-1,2
Up Type=0
Dn Type=3
Dn Slope=0.005
Boundary for River Rch & Prof#=Stream0403,Reach-1,3
Up Type=0
Dn Type=3
Dn Slope=0.005
Boundary for River Rch & Prof#=Stream0403,Reach-1,4
Up Type=0
Dn Type=3
Dn Slope=0.005
Boundary for River Rch & Prof#=Stream0403,Reach-1,5
Up Type=0
Dn Type=3
Dn Slope=0.005
Boundary for River Rch & Prof#=Stream0403,Reach-1,6
Up Type=0
Dn Type=3
Dn Slope=0.005
Boundary for River Rch & Prof#=Stream0403,Reach-1,7
Up Type=0
Dn Type=3
Dn Slope=0.005

--- Stream0403.g01 (geometry) ---

Geom Title=Existing Conditions

River Reach=Stream0403,Reach-1
Reach XY= 30
      1859525.00     13966225.00      1859522.65     13966319.23
      1859486.24     13966365.15      1859484.10     13966381.74
      1859668.94     13966566.86      1859727.17     13966581.15
      1859780.97     13966622.86      1859854.95     13966625.21
      1859873.50     13966621.53      1859884.78     13966614.54
      1859958.25     13966541.47      1859980.86     13966527.07
      1860219.35     13966526.97      1860245.65     13966544.41
      1860271.49     13966576.25      1860275.48     13966659.93
      1860280.42     13966677.75      1860311.37     13966712.05
      1860335.45     13966724.48      1860373.23     13966721.70
      1860422.80     13966681.16      1860477.18     13966668.89
      1860526.56     13966628.76      1860549.92     13966624.81
      1860669.06     13966622.73      1860730.94     13966577.26
      1861059.81     13966574.55      1861081.16     13966567.11
      1861126.51     13966528.65      1861175.00     13966525.00

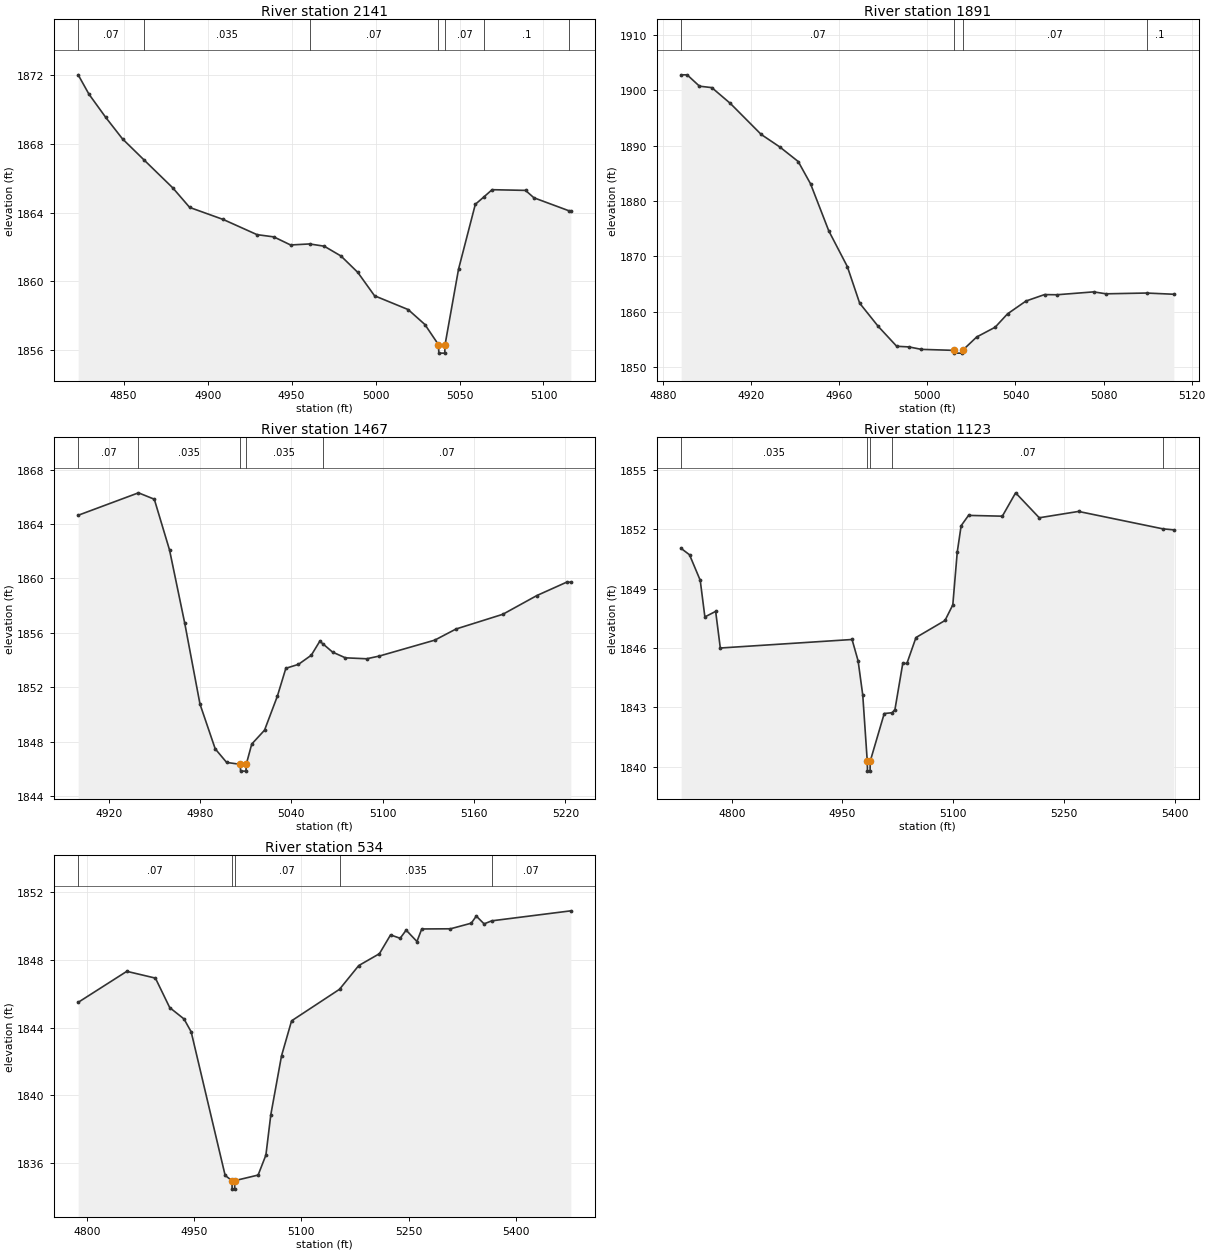
Type RM Length L Ch R = 1,2141,250,250,250
BEGIN DESCRIPTION:
Stream0403 4.0
END DESCRIPTION:
XS GIS Cut Line= 2
      1859348.61     13966270.43      1859641.82     13966280.78
#Sta/Elev= 30
  4822.9 1872.00  4829.3 1870.88  4839.3 1869.53  4849.3 1868.28  4862.1 1867.06
  4879.3 1865.43  4889.3 1864.30  4909.3 1863.60  4929.4 1862.72  4939.4 1862.59
  4949.4 1862.12  4960.7 1862.18  4969.4 1862.05  4979.4 1861.48  4989.4 1860.53
  4999.4 1859.17  5019.4 1858.37  5029.4 1857.50  5037.4 1856.34  5037.7 1855.84
  5041.2 1855.84  5041.4 1856.34  5049.4 1860.71  5059.4 1864.48  5064.5 1864.91
  5069.4 1865.33  5089.3 1865.29  5094.3 1864.86  5115.3 1864.10  5116.3 1864.08
#Mann=7,-1,0
  4822.9    0.07       0  4862.1   0.035       0  4960.7    0.07       0
  5037.4    0.05       0  5041.4    0.07       0  5064.5     0.1       0
  5115.3    0.07       0
Bank Sta=5037.4,5041.4
Exp/Cntr=0.3,0.1

Type RM Length L Ch R = 1,1891,424,424,424
BEGIN DESCRIPTION:
Stream0403 3.0
END DESCRIPTION:
XS GIS Cut Line= 3
      1859475.04     13966524.98      1859575.00     13966475.00
      1859625.02     13966374.97
#Sta/Elev= 30
  4888.3 1902.80  4891.0 1902.80  4896.6 1900.75  4902.2 1900.49  4910.6 1897.64
  4924.6 1892.04  4933.0 1889.79  4941.4 1887.15  4947.0 1883.13  4955.3 1874.61
  4963.7 1868.18  4969.3 1861.57  4977.7 1857.39  4986.1 1853.79  4991.7 1853.67
  4997.3 1853.23  5012.0 1853.05  5012.3 1852.55  5015.8 1852.55  5016.0 1853.05
  5022.4 1855.46  5030.8 1857.23  5036.4 1859.64  5044.8 1861.96  5053.2 1863.12
  5058.8 1863.09  5075.5 1863.61  5081.1 1863.26  5099.5 1863.40  5111.9 1863.18
#Mann=4,-1,0
  4888.3    0.07       0  5012.0    0.05       0  5016.0    0.07       0
  5099.5     0.1       0
Bank Sta=5012,5016
Exp/Cntr=0.3,0.1

Type RM Length L Ch R = 1,1467,344,344,344
BEGIN DESCRIPTION:
Stream0403 2.0
END DESCRIPTION:
XS GIS Cut Line= 3
      1859925.00     13966675.02      1859925.00     13966575.00
      1859825.01     13966375.02
#Sta/Elev= 30
  4900.0 1864.64  4939.6 1866.29  4950.0 1865.82  4960.0 1862.09  4970.0 1856.70
  4980.0 1850.76  4990.0 1847.47  4997.5 1846.47  5006.4 1846.33  5006.7 1845.83
  5010.2 1845.83  5010.4 1846.33  5014.0 1847.82  5022.4 1848.84  5030.8 1851.33
  5036.4 1853.39  5044.7 1853.68  5053.1 1854.35  5058.7 1855.38  5060.5 1855.21
  5067.1 1854.58  5075.5 1854.16  5089.5 1854.09  5097.8 1854.29  5134.2 1855.46
  5148.2 1856.28  5178.9 1857.36  5201.3 1858.74  5220.8 1859.72  5223.6 1859.72
#Mann=5,-1,0
  4900.0    0.07       0  4939.6   0.035       0  5006.4   0.035       0
  5010.4   0.035       0  5060.5    0.07       0
Bank Sta=5006.4,5010.4
Exp/Cntr=0.3,0.1

Type RM Length L Ch R = 1,1123,589,589,589
BEGIN DESCRIPTION:
Stream0403 5.0
END DESCRIPTION:
XS GIS Cut Line= 3
      1860081.21     13966756.53      1860265.23     13966516.96
      1860390.11     13966173.55
#Sta/Elev= 30
  4731.5 1851.03  4742.8 1850.71  4757.3 1849.42  4763.6 1847.57  4778.2 1847.85
  4784.5 1846.00  4963.0 1846.43  4971.2 1845.35  4977.5 1843.62  4983.6 1840.28
  4983.9 1839.78  4987.4 1839.78  4987.6 1840.28  5006.6 1842.69  5017.1 1842.73
  5021.1 1842.89  5031.7 1845.22  5037.3 1845.22  5049.6 1846.53  5088.9 1847.39
  5099.5 1848.18  5105.5 1850.84  5110.8 1852.18  5120.8 1852.70  5166.6 1852.66
  5184.6 1853.84  5216.6 1852.58  5269.8 1852.90  5384.1 1852.02  5399.0 1851.97
#Mann=5,-1,0
  4731.5   0.035       0  4983.6   0.035       0  4987.6   0.035       0
  5017.1    0.07       0  5384.1   0.035       0
Bank Sta=4983.6,4987.6
Exp/Cntr=0.3,0.1

Type RM Length L Ch R = 1,534,0,0,0
BEGIN DESCRIPTION:
Stream0403 1.0
END DESCRIPTION:
XS GIS Cut Line= 3
      1860671.48     13966832.97      1860675.00     13966625.00
      1860483.99     13966183.65
#Sta/Elev= 30
  4787.9 1845.49  4855.9 1847.32  4895.9 1846.92  4915.9 1845.18  4935.9 1844.51
  4945.9 1843.75  4993.4 1835.28  5002.9 1834.97  5003.2 1834.47  5006.7 1834.47
  5006.9 1834.97  5039.5 1835.30  5050.4 1836.48  5057.3 1838.87  5072.2 1842.33
  5086.3 1844.40  5153.3 1846.26  5180.2 1847.66  5209.1 1848.36  5224.7 1849.47
  5238.1 1849.27  5246.5 1849.75  5261.6 1849.08  5268.3 1849.82  5308.5 1849.83
  5337.5 1850.16  5344.6 1850.58  5355.5 1850.12  5366.2 1850.30  5476.8 1850.89
#Mann=5,-1,0
  4787.9    0.07       0  5002.9    0.05       0  5006.9    0.07       0
  5153.3   0.035       0  5366.2    0.07       0
Bank Sta=5002.9,5006.9
Exp/Cntr=0.3,0.1

Chan Stop Cuts=-1