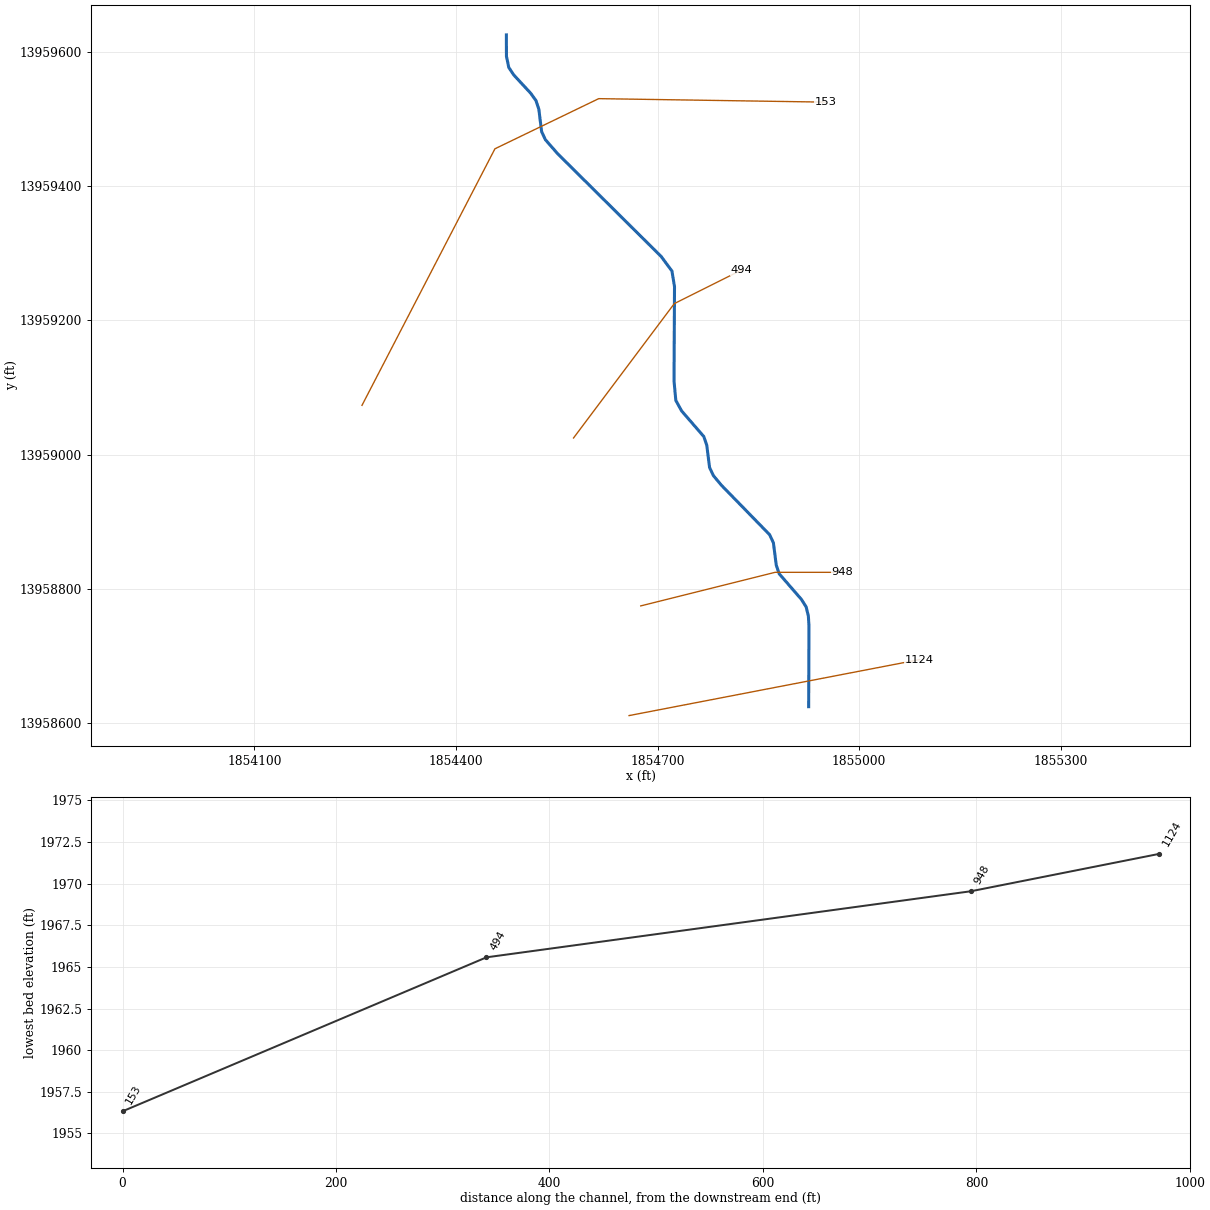
--- Stream0405.prj (project) ---

Proj Title=Stream0405 Base Level Engineering
Current Plan=p01
Default Exp/Contr=0.3,0.1
English Units
Geom File=g01
Flow File=f01
Plan File=p01
Y Axis Title=Elevation
X Axis Title(PF)=Main Channel Distance
X Axis Title(XS)=Station
BEGIN DESCRIPTION:
Stream0405
END DESCRIPTION:
DSS Export Rating Curves= 0
DSS Export Rating Curve Sorted= 0
DSS Export Volume Flow Curves= 0
DXF OffsetX= 0
DXF OffsetY= 0
DXF ScaleX= 1
DXF ScaleY= 10

--- Stream0405.p01 (plan) ---

Plan Title=Multiple Run
Short Identifier=Multiple
Geom File=g01
Flow File=f01
Subcritical Flow
K Sum by GR= 0
Std Step Tol= 0.01
Critical Tol= 0.01
Num of Std Step Trials= 20
Max Error Tol= 0.3
Flow Tol Ratio= 0.001
Split Flow NTrial= 30
Split Flow Tol= 0.02
Split Flow Ratio= 0.02
Log Output Level= 0
Friction Slope Method= 1
Unsteady Friction Slope Method= 2
Unsteady Bridges Friction Slope Method= 1
Parabolic Critical Depth
Global Vel Dist=  1 , 1 , 1
Global Log Level= 0
CheckData=True
Encroach Param= -1, 0, 0, 0
BEGIN DESCRIPTION:
Multiple Run
END DESCRIPTION:

--- Stream0405.f01 (steady flow) ---

Flow Title=Multiple
Program Version=4.10
Number of Profiles= 7
Profile Names=10-year,25-year,50-year,1pct_min,100-year,1pct_plu,500-year
River Rch & RM=Stream0405,Reach-1         ,1124
     950    1609    2233    1499    2992    5969    5300
Boundary for River Rch & Prof#=Stream0405,Reach-1         , 1
Up Type= 0
Dn Type= 3
Dn Slope=0.01
Boundary for River Rch & Prof#=Stream0405,Reach-1         , 2
Up Type= 0
Dn Type= 3
Dn Slope=0.01
Boundary for River Rch & Prof#=Stream0405,Reach-1         , 3
Up Type= 0
Dn Type= 3
Dn Slope=0.01
Boundary for River Rch & Prof#=Stream0405,Reach-1         , 4
Up Type= 0
Dn Type= 3
Dn Slope=0.01
Boundary for River Rch & Prof#=Stream0405,Reach-1         , 5
Up Type= 0
Dn Type= 3
Dn Slope=0.01
Boundary for River Rch & Prof#=Stream0405,Reach-1         , 6
Up Type= 0
Dn Type= 3
Dn Slope=0.01
Boundary for River Rch & Prof#=Stream0405,Reach-1         , 7
Up Type= 0
Dn Type= 3
Dn Slope=0.01
DSS Import GetInterval= 0
DSS Import GetPeak= 0
DSS Import FillOption= 0

--- Stream0405.g01 (geometry) ---

Geom Title=Existing Conditions

River Reach=Stream0405,Reach-1
Reach XY= 30
      1854925.00     13958625.00      1854925.44     13958745.18
      1854924.55     13958759.82      1854921.28     13958773.46
      1854914.21     13958784.67      1854881.14     13958822.83
      1854876.72     13958835.71      1854872.50     13958868.96
      1854866.84     13958881.05      1854794.82     13958954.93
      1854783.16     13958968.95      1854777.50     13958981.04
      1854773.28     13959014.29      1854768.86     13959027.17
      1854735.79     13959065.33      1854727.24     13959080.93
      1854724.57     13959109.82      1854725.29     13959250.12
      1854721.46     13959273.54      1854705.40     13959295.16
      1854551.29     13959448.18      1854533.13     13959468.94
      1854527.47     13959481.02      1854523.34     13959514.31
      1854519.03     13959527.24      1854511.22     13959538.15
      1854485.98     13959565.40      1854478.60     13959576.49
      1854475.10     13959593.19      1854475.00     13959625.00

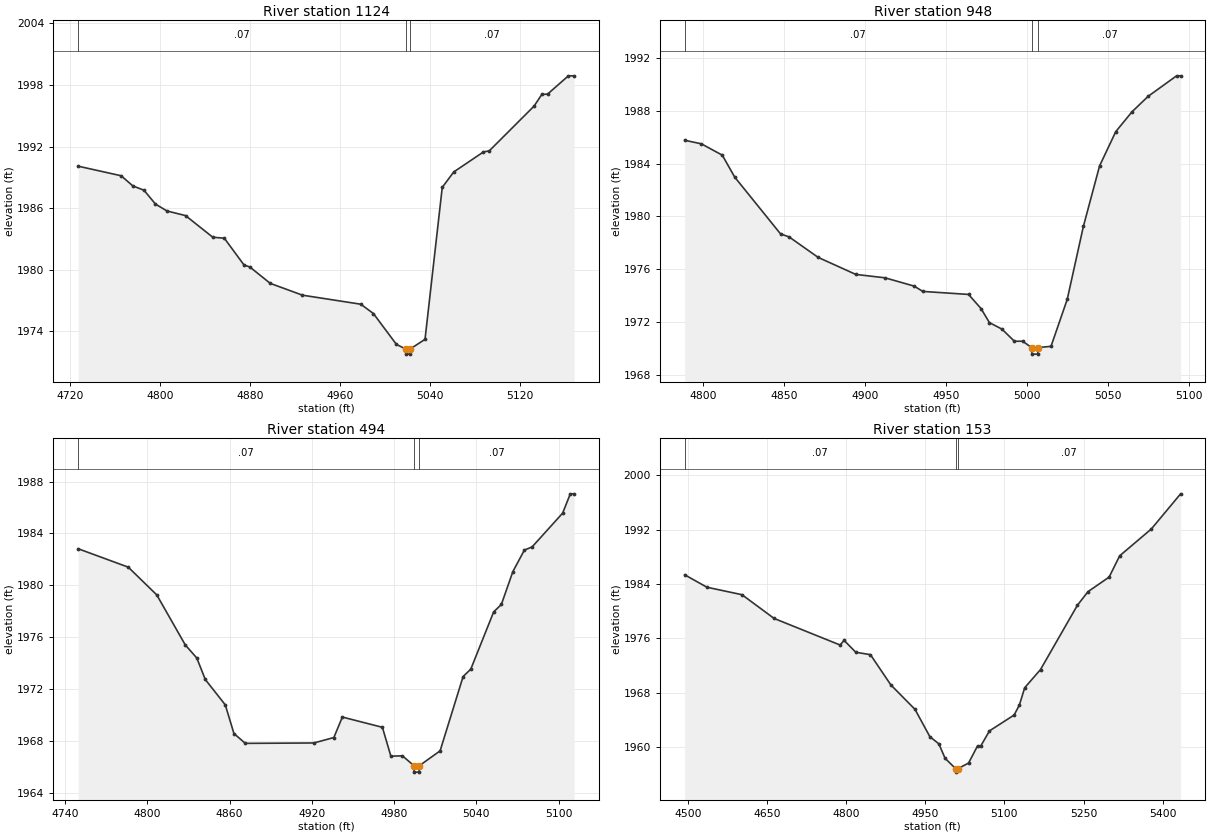
Type RM Length L Ch R = 1,1124,176,176,176
BEGIN DESCRIPTION:
Stream0405 3.0
END DESCRIPTION:
XS GIS Cut Line= 2
      1854657.62     13958611.73      1855089.96     13958695.07
#Sta/Elev= 30
  4727.6 1990.09  4765.7 1989.16  4776.1 1988.17  4786.0 1987.75  4796.2 1986.40
  4806.4 1985.73  4822.9 1985.28  4847.1 1983.17  4857.3 1983.08  4874.8 1980.47
  4879.9 1980.28  4898.1 1978.68  4926.7 1977.53  4978.5 1976.65  4989.7 1975.74
  5010.1 1972.74  5018.3 1972.29  5018.5 1971.79  5022.0 1971.79  5022.3 1972.29
  5035.5 1973.23  5050.8 1988.03  5061.0 1989.53  5087.4 1991.48  5092.5 1991.58
  5132.3 1995.94  5139.2 1997.08  5144.3 1997.11  5162.8 1998.89  5167.9 1998.89
#Mann=3,-1,0
  4727.6    0.07       0  5018.3    0.05       0  5022.3    0.07       0
Bank Sta=5018.3,5022.3
Exp/Cntr=0.3,0.1

Type RM Length L Ch R = 1,948,454,454,454
BEGIN DESCRIPTION:
Stream0405 2.0
END DESCRIPTION:
XS GIS Cut Line= 3
      1854675.03     13958775.01      1854875.00     13958825.00
      1854974.97     13958825.00
#Sta/Elev= 30
  4788.8 1985.78  4799.1 1985.51  4812.0 1984.65  4819.7 1982.98  4848.0 1978.67
  4853.2 1978.45  4871.2 1976.89  4894.4 1975.60  4912.5 1975.34  4930.5 1974.71
  4935.7 1974.31  4964.0 1974.08  4971.7 1973.01  4976.9 1971.94  4984.6 1971.45
  4992.3 1970.53  4997.4 1970.53  5002.9 1970.05  5003.2 1969.55  5006.7 1969.55
  5006.9 1970.05  5014.9 1970.14  5024.9 1973.70  5034.9 1979.25  5044.9 1983.84
  5054.9 1986.44  5064.9 1987.94  5074.9 1989.12  5092.4 1990.67  5094.9 1990.67
#Mann=3,-1,0
  4788.8    0.07       0  5002.9    0.05       0  5006.9    0.07       0
Bank Sta=5002.9,5006.9
Exp/Cntr=0.3,0.1

Type RM Length L Ch R = 1,494,341,341,341
BEGIN DESCRIPTION:
Stream0405 1.0
END DESCRIPTION:
XS GIS Cut Line= 3
      1854574.99     13959024.99      1854725.00     13959225.00
      1854824.98     13959274.99
#Sta/Elev= 30
  4749.5 1982.82  4786.0 1981.40  4806.8 1979.26  4827.6 1975.40  4836.0 1974.39
  4842.2 1972.73  4856.8 1970.77  4863.1 1968.56  4871.4 1967.80  4921.4 1967.83
  4936.0 1968.25  4942.2 1969.83  4971.4 1969.04  4977.6 1966.81  4986.0 1966.84
  4994.4 1966.08  4994.6 1965.58  4998.1 1965.58  4998.4 1966.08  5013.5 1967.22
  5030.3 1972.96  5035.9 1973.53  5052.6 1977.95  5058.2 1978.52  5066.6 1981.06
  5075.0 1982.72  5080.6 1982.96  5102.9 1985.57  5108.5 1987.06  5111.3 1987.06
#Mann=3,-1,0
  4749.5    0.07       0  4994.4    0.05       0  4998.4    0.07       0
Bank Sta=4994.4,4998.4
Exp/Cntr=0.3,0.1

Type RM Length L Ch R = 1,153,0,0,0
BEGIN DESCRIPTION:
Stream0405 0.0
END DESCRIPTION:
XS GIS Cut Line= 4
      1854260.06     13959073.55      1854457.97     13959455.48
      1854612.48     13959530.13      1854950.48     13959524.93
#Sta/Elev= 30
  4494.2 1985.36  4536.4 1983.53  4602.8 1982.43  4663.6 1978.94  4788.7 1975.03
  4796.3 1975.71  4818.5 1973.96  4846.2 1973.61  4884.9 1969.16  4930.7 1965.56
  4958.8 1961.55  4975.9 1960.49  4987.7 1958.36  5007.9 1956.83  5008.2 1956.33
  5011.9 1956.83  5032.2 1957.67  5049.2 1960.19  5054.8 1960.11  5071.8 1962.40
  5118.5 1964.73  5128.5 1966.21  5138.5 1968.74  5168.5 1971.42  5238.5 1980.89
  5258.5 1982.88  5298.5 1985.02  5318.5 1988.15  5378.5 1992.10  5434.0 1997.27
#Mann=3,-1,0
  4494.2    0.07       0  5007.9    0.05       0  5011.9    0.07       0
Bank Sta=5007.9,5011.9
Exp/Cntr=0.3,0.1

Chan Stop Cuts=-1