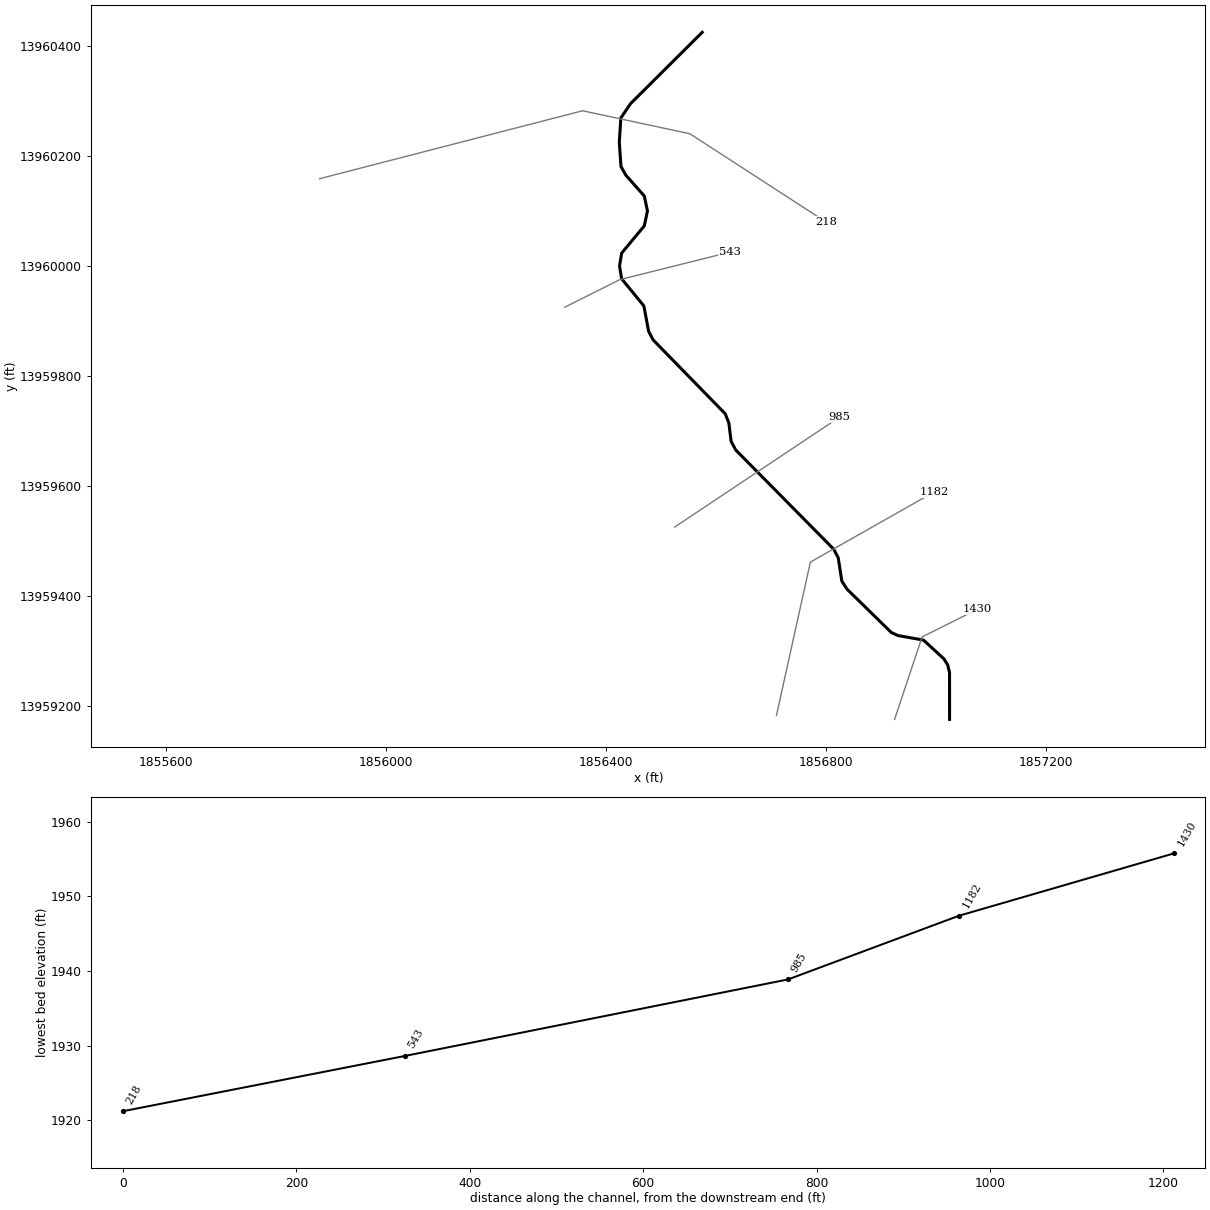
--- Stream0406.prj (project) ---

Proj Title=Stream0406 Base Level Engineering
Current Plan=p01
Default Exp/Contr=0.3,0.1
English Units
Geom File=g01
Flow File=f01
Plan File=p01
BEGIN DESCRIPTION:
Stream0406
END DESCRIPTION:

--- Stream0406.p01 (plan) ---

Plan Title=Multiple Run
Short Identifier=Multiple
Geom File=g01
Flow File=f01
Subcritical Flow
K Sum by GR= 0
Std Step Tol= 0.01
Critical Tol= 0.01
Num of Std Step Trials= 20
Max Error Tol= 0.3
Flow Tol Ratio= 0.001
Split Flow NTrial= 30
Split Flow Tol= 0.02
Split Flow Ratio= 0.02
Log Output Level= 0
Friction Slope Method= 1
Unsteady Friction Slope Method= 2
Unsteady Bridges Friction Slope Method= 1
Parabolic Critical Depth
Global Vel Dist=  1 , 1 , 1
Global Log Level= 0
CheckData=True
Encroach Param= -1, 0, 0, 0
BEGIN DESCRIPTION:
Multiple Run
END DESCRIPTION:

--- Stream0406.f01 (steady flow) ---

Flow Title=Multiple
Number of Profiles=7
Profile Names=10-year,25-year,50-year,1pct_min,100-year,1pct_plu,500-year
River Rch & RM= Stream0406,Reach-1,1430
     518     845    1144     751    1499    2992    2537
Boundary for River Rch & Prof#=Stream0406,Reach-1,1
Up Type=0
Dn Type=3
Dn Slope=0.005
Boundary for River Rch & Prof#=Stream0406,Reach-1,2
Up Type=0
Dn Type=3
Dn Slope=0.005
Boundary for River Rch & Prof#=Stream0406,Reach-1,3
Up Type=0
Dn Type=3
Dn Slope=0.005
Boundary for River Rch & Prof#=Stream0406,Reach-1,4
Up Type=0
Dn Type=3
Dn Slope=0.005
Boundary for River Rch & Prof#=Stream0406,Reach-1,5
Up Type=0
Dn Type=3
Dn Slope=0.005
Boundary for River Rch & Prof#=Stream0406,Reach-1,6
Up Type=0
Dn Type=3
Dn Slope=0.005
Boundary for River Rch & Prof#=Stream0406,Reach-1,7
Up Type=0
Dn Type=3
Dn Slope=0.005

--- Stream0406.g01 (geometry) ---

Geom Title=Existing Conditions

River Reach=Stream0406,Reach-1
Reach XY= 30
      1857025.00     13959175.00      1857024.95     13959260.11
      1857021.72     13959273.85      1857014.71     13959285.18
      1856977.57     13959319.27      1856931.08     13959327.54
      1856918.95     13959333.16      1856838.62     13959411.76
      1856828.97     13959426.64      1856822.46     13959468.95
      1856814.22     13959484.68      1856635.78     13959665.32
      1856627.53     13959681.05      1856623.45     13959714.36
      1856616.84     13959731.05      1856485.76     13959865.32
      1856477.49     13959881.04      1856468.82     13959927.19
      1856428.34     13959976.72      1856424.60     13960000.00
      1856428.40     13960023.28      1856469.59     13960072.80
      1856475.39     13960100.00      1856469.62     13960127.18
      1856435.87     13960165.35      1856427.19     13960180.97
      1856424.15     13960225.01      1856426.96     13960269.11
      1856444.57     13960295.16      1856575.00     13960425.00

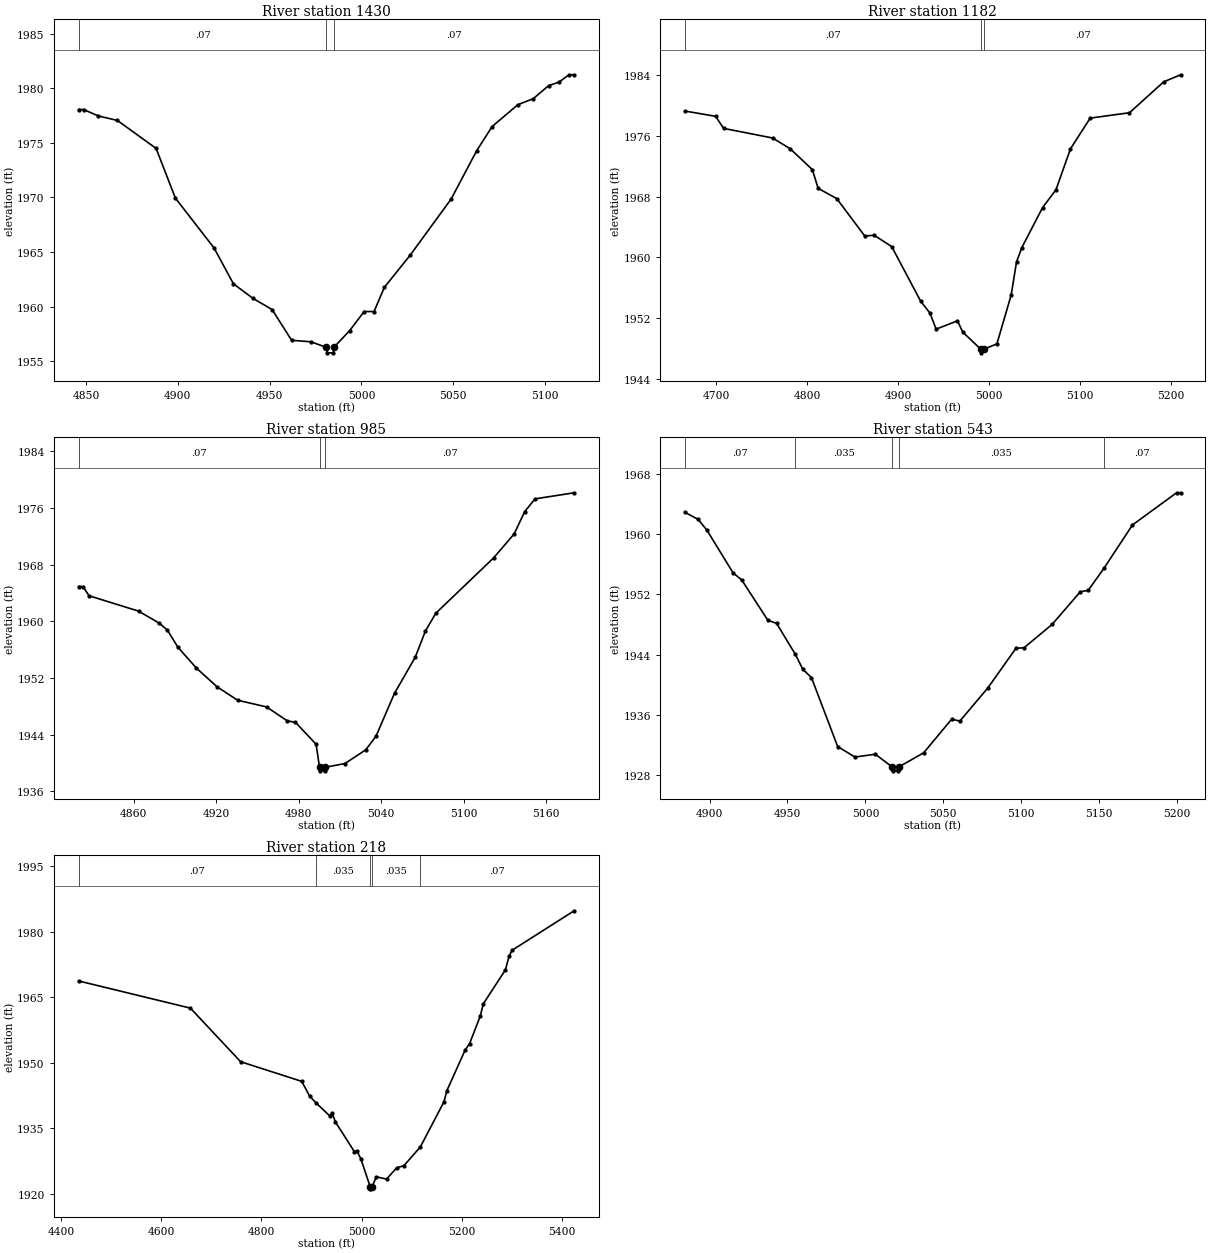
Type RM Length L Ch R = 1,1430,248,248,248
BEGIN DESCRIPTION:
Stream0406 3.0
END DESCRIPTION:
XS GIS Cut Line= 3
      1856925.00     13959174.99      1856975.00     13959325.00
      1857074.97     13959374.99
#Sta/Elev= 30
  4846.0 1978.05  4848.7 1978.05  4856.6 1977.47  4867.1 1977.05  4888.2 1974.49
  4898.7 1969.94  4919.8 1965.37  4930.3 1962.10  4940.9 1960.77  4951.4 1959.74
  4962.0 1956.93  4972.5 1956.79  4981.0 1956.28  4981.3 1955.78  4984.8 1955.78
  4985.0 1956.28  4993.6 1957.81  5001.5 1959.56  5006.9 1959.56  5012.5 1961.77
  5026.5 1964.70  5048.9 1969.86  5062.8 1974.28  5071.2 1976.49  5085.2 1978.49
  5093.6 1979.04  5102.0 1980.24  5107.5 1980.55  5113.1 1981.23  5115.9 1981.23
#Mann=3,-1,0
  4846.0    0.07       0  4981.0    0.05       0  4985.0    0.07       0
Bank Sta=4981,4985
Exp/Cntr=0.3,0.1

Type RM Length L Ch R = 1,1182,197,197,197
BEGIN DESCRIPTION:
Stream0406 4.0
END DESCRIPTION:
XS GIS Cut Line= 3
      1856710.05     13959182.26      1856771.82     13959461.23
      1856996.98     13959588.76
#Sta/Elev= 30
  4665.9 1979.26  4699.4 1978.57  4708.2 1976.98  4762.1 1975.71  4781.4 1974.29
  4805.7 1971.55  4812.1 1969.08  4832.6 1967.72  4863.3 1962.80  4873.6 1962.90
  4892.9 1961.41  4924.8 1954.20  4935.0 1952.64  4941.7 1950.53  4965.2 1951.63
  4971.0 1950.14  4990.6 1947.91  4990.9 1947.41  4994.6 1947.91  5008.5 1948.59
  5024.2 1955.03  5030.1 1959.41  5035.9 1961.27  5058.7 1966.55  5073.4 1968.89
  5089.3 1974.27  5111.0 1978.33  5154.2 1979.04  5191.8 1983.11  5210.4 1984.04
#Mann=3,-1,0
  4665.9    0.07       0  4990.6    0.05       0  4994.6    0.07       0
Bank Sta=4990.6,4994.6
Exp/Cntr=0.3,0.1

Type RM Length L Ch R = 1,985,442,442,442
BEGIN DESCRIPTION:
Stream0406 2.0
END DESCRIPTION:
XS GIS Cut Line= 3
      1856524.96     13959524.97      1856675.00     13959625.00
      1856825.00     13959725.00
#Sta/Elev= 30
  4819.9 1964.89  4823.0 1964.89  4827.5 1963.59  4863.5 1961.42  4878.5 1959.73
  4884.5 1958.74  4892.1 1956.33  4905.6 1953.38  4920.6 1950.74  4935.6 1948.84
  4956.7 1947.89  4971.7 1945.93  4977.7 1945.72  4992.7 1942.62  4995.2 1939.37
  4995.5 1938.87  4999.0 1938.87  4999.2 1939.37  5013.7 1939.90  5028.8 1941.83
  5036.3 1943.76  5049.8 1949.84  5064.8 1954.89  5072.3 1958.63  5079.8 1961.12
  5121.9 1968.94  5136.9 1972.34  5144.4 1975.44  5152.0 1977.27  5180.5 1978.13
#Mann=3,-1,0
  4819.9    0.07       0  4995.2    0.05       0  4999.2    0.07       0
Bank Sta=4995.2,4999.2
Exp/Cntr=0.3,0.1

Type RM Length L Ch R = 1,543,325,325,325
BEGIN DESCRIPTION:
Stream0406 1.0
END DESCRIPTION:
XS GIS Cut Line= 3
      1856324.97     13959924.98      1856425.00     13959975.00
      1856625.00     13960025.00
#Sta/Elev= 30
  4884.3 1962.87  4892.7 1961.94  4898.3 1960.51  4915.1 1954.85  4920.7 1953.89
  4937.4 1948.57  4943.0 1948.16  4955.1 1944.03  4959.8 1942.08  4965.4 1940.96
  4982.2 1931.82  4993.3 1930.43  5006.4 1930.80  5017.3 1929.10  5017.6 1928.60
  5021.1 1928.60  5021.3 1929.10  5037.4 1930.99  5055.4 1935.46  5060.6 1935.19
  5078.6 1939.60  5096.6 1944.85  5101.8 1944.92  5119.8 1948.01  5137.9 1952.34
  5143.0 1952.54  5153.2 1955.49  5171.4 1961.21  5199.7 1965.47  5202.3 1965.47
#Mann=5,-1,0
  4884.3    0.07       0  4955.1   0.035       0  5017.3   0.035       0
  5021.3   0.035       0  5153.2    0.07       0
Bank Sta=5017.3,5021.3
Exp/Cntr=0.3,0.1

Type RM Length L Ch R = 1,218,0,0,0
BEGIN DESCRIPTION:
Stream0406 0.0
END DESCRIPTION:
XS GIS Cut Line= 4
      1855879.05     13960158.69      1856357.33     13960282.25
      1856552.62     13960240.40      1856800.10     13960080.03
#Sta/Elev= 30
  4435.2 1968.70  4658.2 1962.49  4758.3 1950.25  4880.3 1945.75  4895.8 1942.43
  4908.9 1940.82  4935.9 1937.89  4941.0 1938.54  4947.3 1936.51  4985.3 1929.69
  4990.4 1929.86  4998.4 1928.00  5016.8 1921.69  5017.1 1921.19  5020.8 1921.69
  5029.1 1923.94  5049.5 1923.43  5070.0 1926.01  5084.2 1926.48  5117.0 1930.79
  5164.0 1941.07  5169.9 1943.65  5206.2 1952.89  5215.2 1954.39  5236.5 1960.69
  5242.5 1963.47  5286.6 1971.23  5293.9 1974.33  5299.8 1975.71  5423.8 1984.74
#Mann=5,-1,0
  4435.2    0.07       0  4908.9   0.035       0  5016.8   0.035       0
  5020.8   0.035       0  5117.0    0.07       0
Bank Sta=5016.8,5020.8
Exp/Cntr=0.3,0.1

Chan Stop Cuts=-1