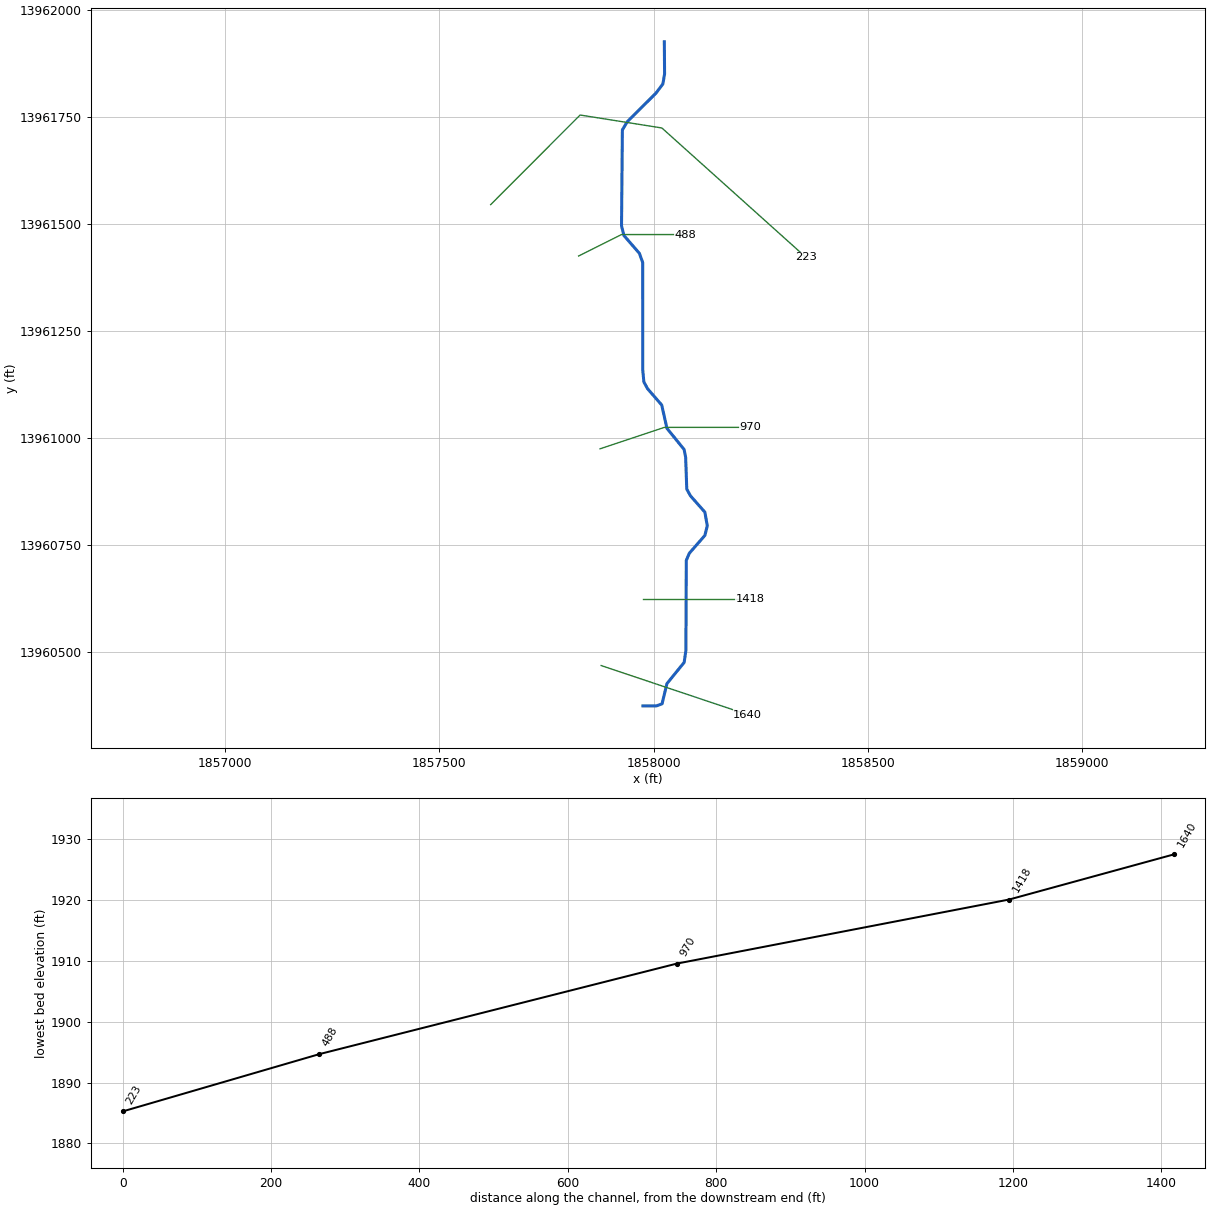
--- Stream0408.prj (project) ---

Proj Title=Stream0408 Base Level Engineering
Current Plan=p01
Default Exp/Contr=0.3,0.1
English Units
Geom File=g01
Flow File=f01
Plan File=p01
Y Axis Title=Elevation
X Axis Title(PF)=Main Channel Distance
X Axis Title(XS)=Station
BEGIN DESCRIPTION:
Stream0408
END DESCRIPTION:
DSS Export Rating Curves= 0
DSS Export Rating Curve Sorted= 0
DSS Export Volume Flow Curves= 0
DXF OffsetX= 0
DXF OffsetY= 0
DXF ScaleX= 1
DXF ScaleY= 10

--- Stream0408.p01 (plan) ---

Plan Title=Multiple Run
Short Identifier=Multiple
Geom File=g01
Flow File=f01
Subcritical Flow
K Sum by GR= 0
Std Step Tol= 0.01
Critical Tol= 0.01
Num of Std Step Trials= 20
Max Error Tol= 0.3
Flow Tol Ratio= 0.001
Split Flow NTrial= 30
Split Flow Tol= 0.02
Split Flow Ratio= 0.02
Log Output Level= 0
Friction Slope Method= 1
Unsteady Friction Slope Method= 2
Unsteady Bridges Friction Slope Method= 1
Parabolic Critical Depth
Global Vel Dist=  1 , 1 , 1
Global Log Level= 0
CheckData=True
Encroach Param= -1, 0, 0, 0
BEGIN DESCRIPTION:
Multiple Run
END DESCRIPTION:

--- Stream0408.f01 (steady flow) ---

Flow Title=Multiple
Number of Profiles=7
Profile Names=10-year,25-year,50-year,1pct_min,100-year,1pct_plu,500-year
River Rch & RM= Stream0408,Reach-1,1640
     436     703     944     616    1228    2451    2048
Boundary for River Rch & Prof#=Stream0408,Reach-1,1
Up Type=0
Dn Type=3
Dn Slope=0.005
Boundary for River Rch & Prof#=Stream0408,Reach-1,2
Up Type=0
Dn Type=3
Dn Slope=0.005
Boundary for River Rch & Prof#=Stream0408,Reach-1,3
Up Type=0
Dn Type=3
Dn Slope=0.005
Boundary for River Rch & Prof#=Stream0408,Reach-1,4
Up Type=0
Dn Type=3
Dn Slope=0.005
Boundary for River Rch & Prof#=Stream0408,Reach-1,5
Up Type=0
Dn Type=3
Dn Slope=0.005
Boundary for River Rch & Prof#=Stream0408,Reach-1,6
Up Type=0
Dn Type=3
Dn Slope=0.005
Boundary for River Rch & Prof#=Stream0408,Reach-1,7
Up Type=0
Dn Type=3
Dn Slope=0.005

--- Stream0408.g01 (geometry) ---

Geom Title=Existing Conditions
Program Version=4.10

River Reach=Stream0408      ,Reach-1
Reach XY= 30
        1857975.       13960375.      1858006.56     13960375.06
      1858019.72      13960379.9      1858031.04       13960427.
      1858071.28     13960476.52      1858075.37     13960504.84
      1858076.24      13960714.5      1858083.19     13960731.08
      1858119.62     13960772.82      1858125.28     13960795.18
      1858119.63     13960827.18      1858085.95     13960865.35
      1858077.38     13960880.97      1858074.77      13960954.9
      1858071.17     13960973.42      1858031.11     13961022.82
      1858018.88     13961077.18       1857985.8     13961115.33
      1857977.24     13961130.93      1857974.56     13961159.82
      1857974.48     13961409.78      1857966.86     13961431.06
      1857930.75     13961472.67      1857925.07     13961495.03
      1857927.06     13961719.14       1857938.4     13961738.31
      1858005.34     13961804.86      1858021.61     13961826.41
      1858025.59     13961849.76        1858025.       13961925.

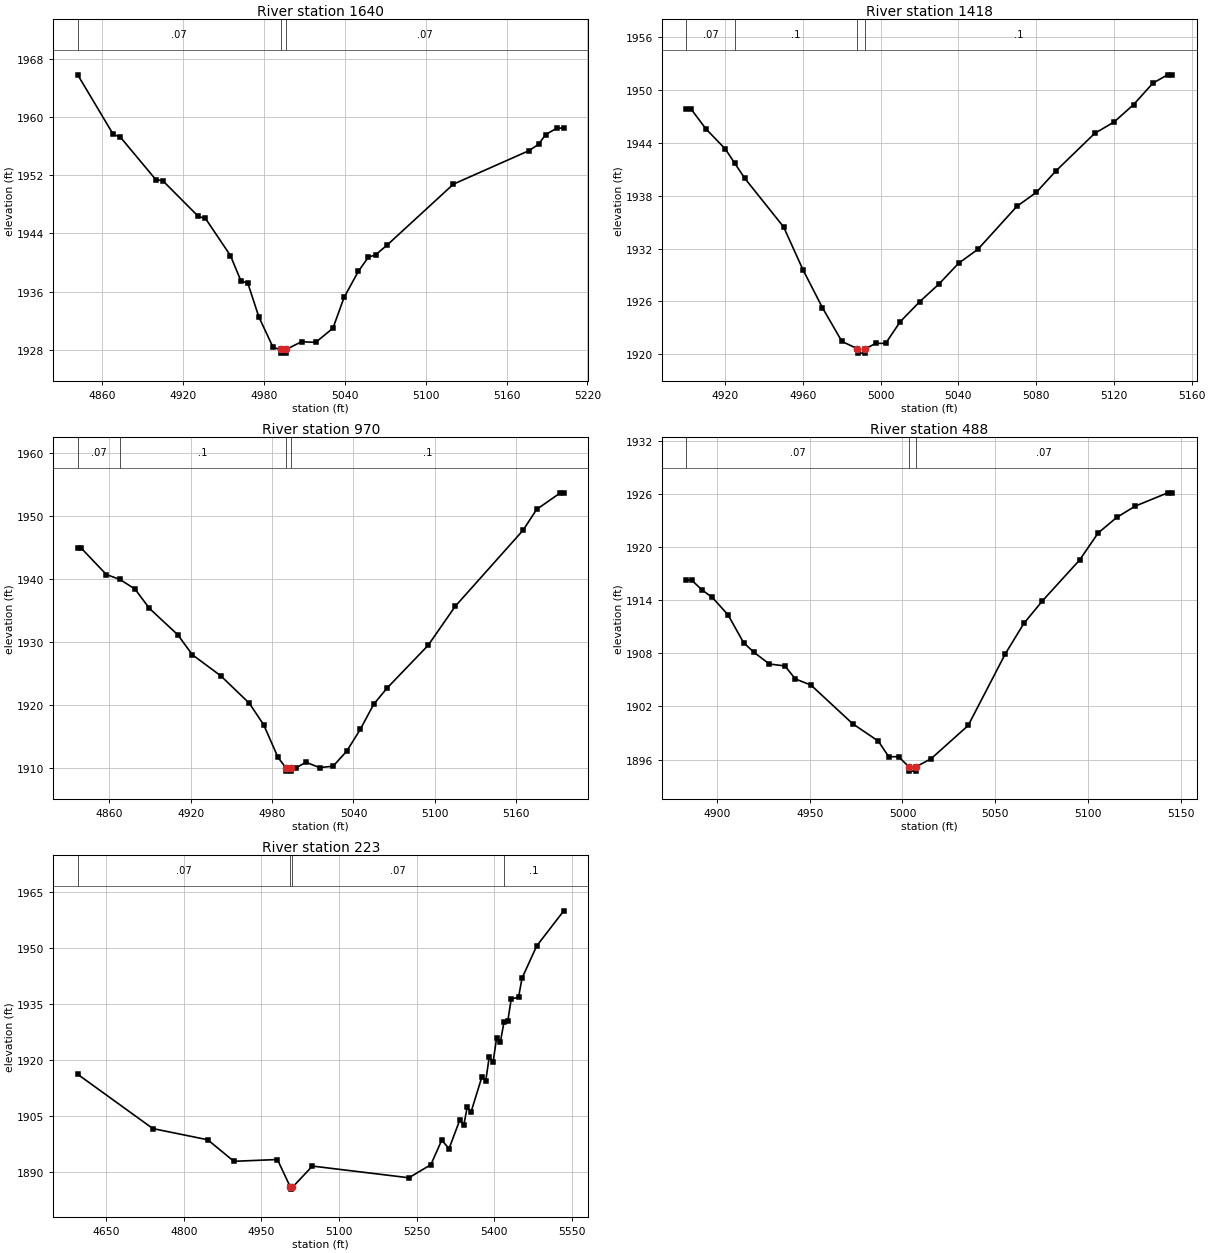
Type RM Length L Ch R = 1 ,1640    ,222,222,222
BEGIN DESCRIPTION:
Stream0408 4.0
END DESCRIPTION:
XS GIS Cut Line= 2
      1857877.53     13960469.22      1858219.54     13960354.64
#Sta/Elev= 30
  4841.7 1965.83  4868.1 1957.62  4873.3 1957.27  4899.6 1951.42  4904.9 1951.25
  4931.2 1946.35  4936.5 1946.07    4955 1940.97  4962.7 1937.53    4968 1937.13
  4976.1 1932.53  4986.7 1928.32  4992.3 1928.04  4992.5 1927.54    4996 1927.54
  4996.3 1928.04  5007.8 1929.11  5018.3 1929.02  5031.1 1930.97  5039.4 1935.22
    5050 1938.81  5057.4 1940.74  5062.7 1941.06  5071.1 1942.37  5120.5 1950.79
  5176.5 1955.39  5183.7 1956.27  5188.9 1957.61  5197.4  1958.5  5202.4  1958.5
#Mann= 3 ,-1 , 0
  4841.7     .07       0  4992.3     .05       0  4996.3     .07       0
Bank Sta=4992.3,4996.3
XS Rating Curve= 0 ,0
Exp/Cntr=0.3,0.1

Type RM Length L Ch R = 1 ,1418    ,448,448,448
BEGIN DESCRIPTION:
Stream0408 3.0
END DESCRIPTION:
XS GIS Cut Line= 3
      1857975.02       13960625.        1858075.       13960625.
      1858225.02       13960625.
#Sta/Elev= 30
  4900.1 1947.84  4902.6 1947.84  4910.1 1945.62  4920.1 1943.33    4925  1941.7
  4930.1    1940  4950.1 1934.47  4960.1 1929.59  4970.1 1925.28  4980.1 1921.45
  4988.1 1920.62  4988.3 1920.12  4991.8 1920.12  4992.1 1920.62  4997.6 1921.23
  5002.6 1921.23  5010.1 1923.69  5020.1 1925.96  5030.1 1927.99  5040.1 1930.33
  5050.1 1931.93  5070.1  1936.8  5080.1 1938.39  5090.1 1940.81  5110.1 1945.09
  5120.1 1946.39  5130.1 1948.36  5140.1 1950.81  5147.6 1951.75  5150.1 1951.75
#Mann= 4 ,-1 , 0
  4900.1     .07       0    4925      .1       0  4988.1     .05       0
  4992.1      .1       0
Bank Sta=4988.1,4992.1
XS Rating Curve= 0 ,0
Exp/Cntr=0.3,0.1

Type RM Length L Ch R = 1 ,970     ,482,482,482
BEGIN DESCRIPTION:
Stream0408 2.0
END DESCRIPTION:
XS GIS Cut Line= 3
      1857874.96     13960974.99        1858025.       13961025.
      1858225.04       13961025.
#Sta/Elev= 30
  4836.8 1944.94  4839.5 1944.94  4857.9 1940.77  4867.8 1940.01    4879 1938.47
  4889.6 1935.41  4910.6  1931.2  4921.2 1928.06  4942.3 1924.69  4963.3 1920.34
  4973.9 1916.91  4984.4 1911.76  4990.3 1910.08  4990.6 1909.58  4994.1 1909.58
  4994.3 1910.08  4997.5 1910.08    5005 1910.99    5015 1910.14    5025 1910.36
    5035 1912.74    5045 1916.19    5055 1920.22    5065 1922.81    5095 1929.53
    5115 1935.73    5165  1947.8    5175 1951.11  5192.5 1953.74    5195 1953.74
#Mann= 4 ,-1 , 0
  4836.8     .07       0  4867.8      .1       0  4990.3     .05       0
  4994.3      .1       0
Bank Sta=4990.3,4994.3
XS Rating Curve= 0 ,0
Exp/Cntr=0.3,0.1

Type RM Length L Ch R = 1 ,488     ,265,265,265
BEGIN DESCRIPTION:
Stream0408 1.0
END DESCRIPTION:
XS GIS Cut Line= 3
      1857824.98     13961424.99        1857925.       13961475.
      1858074.97       13961475.
#Sta/Elev= 30
  4883.6 1916.29  4886.4 1916.29    4892 1915.18  4897.6 1914.32    4906 1912.37
  4914.4 1909.22    4920 1908.12  4928.3  1906.8  4936.7 1906.58  4942.3 1905.11
  4950.7 1904.42  4973.1 1900.06    4987 1898.08  4992.6 1896.32  4997.9 1896.32
  5003.4 1895.19  5003.7 1894.69  5007.2 1894.69  5007.4 1895.19  5015.4 1896.09
  5035.4 1899.85  5055.4 1907.95  5065.4 1911.39  5075.4 1913.94  5095.4 1918.55
  5105.4 1921.61  5115.4 1923.37  5125.4 1924.65  5142.9 1926.15  5145.4 1926.15
#Mann= 3 ,-1 , 0
  4883.6     .07       0  5003.4     .05       0  5007.4     .07       0
Bank Sta=5003.4,5007.4
XS Rating Curve= 0 ,0
Exp/Cntr=0.3,0.1

Type RM Length L Ch R = 1 ,223     ,0,0,0
BEGIN DESCRIPTION:
Stream0408 0.0
END DESCRIPTION:
XS GIS Cut Line= 4
      1857619.61      13961544.8      1857828.37     13961753.96
      1858019.27     13961723.72      1858355.51     13961421.94
#Sta/Elev= 30
  4594.4  1916.1  4739.8 1901.53  4845.9 1898.53  4896.6 1892.74  4980.9 1893.22
    5006 1885.77  5006.3 1885.27    5010 1885.77  5048.5 1891.46  5235.2 1888.32
  5277.8 1891.83  5298.8 1898.42    5313 1896.15  5333.9 1903.87  5341.4 1902.38
  5348.1 1907.25  5355.6    1906  5376.5  1915.4    5384 1914.36  5390.7 1920.71
  5398.2 1919.36  5404.9 1925.78  5412.4 1924.88  5419.4 1930.18  5426.6 1930.35
  5433.3 1936.36  5447.5  1936.8  5454.2 1941.93  5482.7  1950.6    5535 1960.01
#Mann= 4 ,-1 , 0
  4594.4     .07       0    5006     .05       0    5010     .07       0
  5419.4      .1       0
Bank Sta=5006,5010
XS Rating Curve= 0 ,0
Exp/Cntr=0.3,0.1

Chan Stop Cuts=-1
Use User Specified Reach Order=0
Composite Channel Slope=5