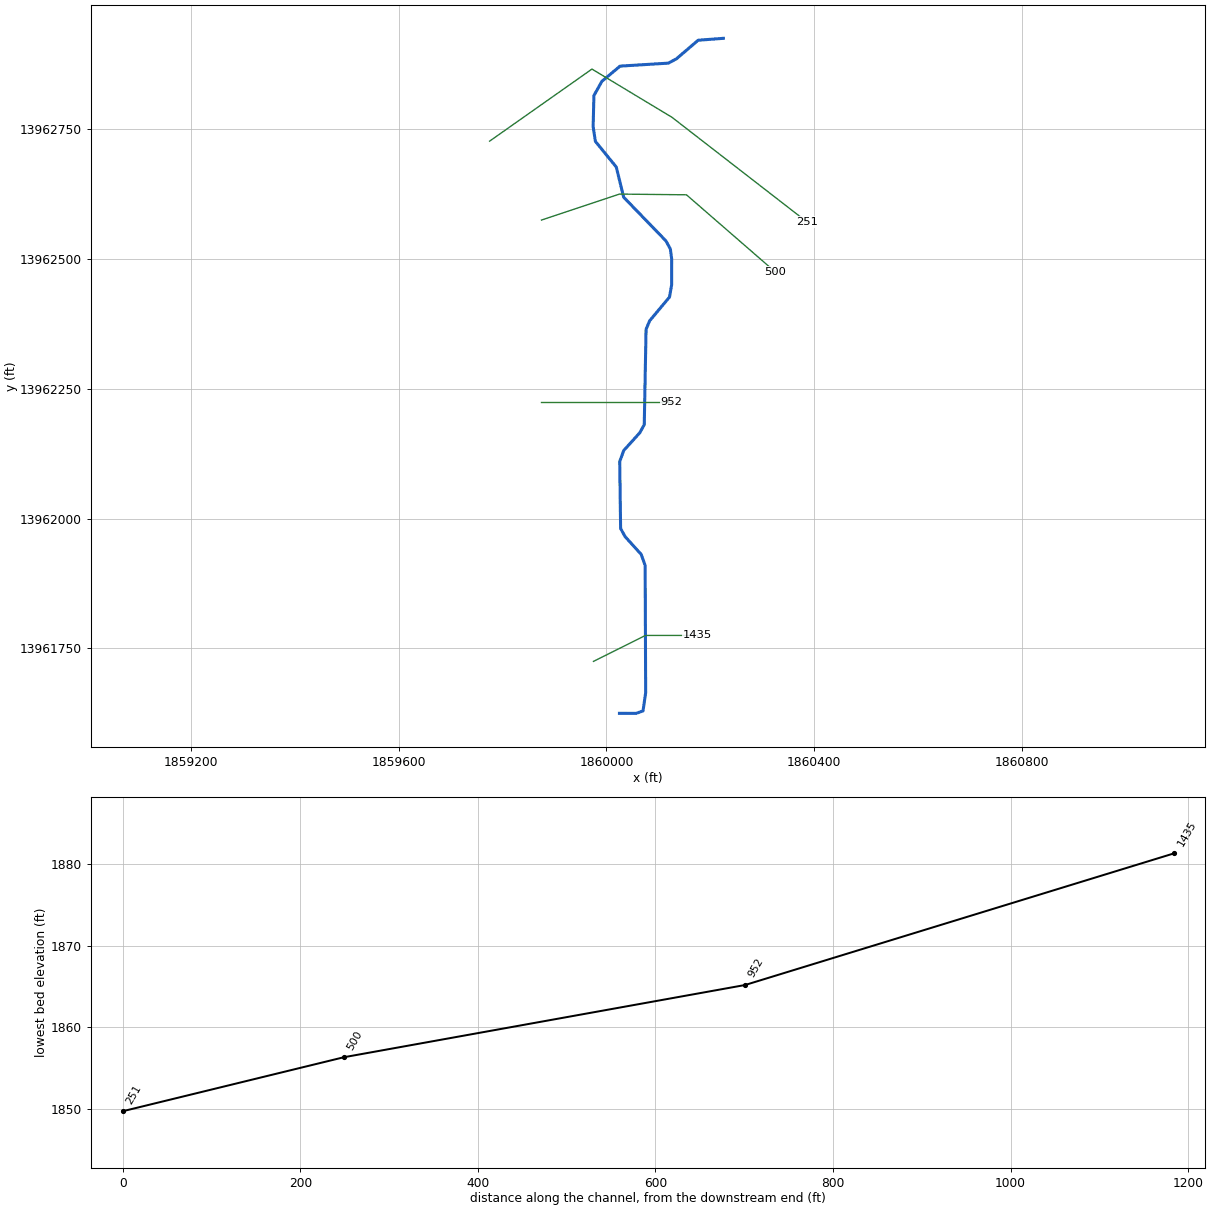
--- Stream0409.prj (project) ---

Proj Title=Stream0409 Base Level Engineering
Current Plan=p01
Default Exp/Contr=0.3,0.1
English Units
Geom File=g01
Flow File=f01
Plan File=p01
BEGIN DESCRIPTION:
Stream0409
END DESCRIPTION:

--- Stream0409.p01 (plan) ---

Plan Title=Multiple Run
Short Identifier=Multiple
Geom File=g01
Flow File=f01
Subcritical Flow
K Sum by GR= 0
Std Step Tol= 0.01
Critical Tol= 0.01
Num of Std Step Trials= 20
Max Error Tol= 0.3
Flow Tol Ratio= 0.001
Split Flow NTrial= 30
Split Flow Tol= 0.02
Split Flow Ratio= 0.02
Log Output Level= 0
Friction Slope Method= 1
Unsteady Friction Slope Method= 2
Unsteady Bridges Friction Slope Method= 1
Parabolic Critical Depth
Global Vel Dist=  1 , 1 , 1
Global Log Level= 0
CheckData=True
Encroach Param= -1, 0, 0, 0
BEGIN DESCRIPTION:
Multiple Run
END DESCRIPTION:

--- Stream0409.f01 (steady flow) ---

Flow Title=Multiple
Number of Profiles=7
Profile Names=10-year,25-year,50-year,1pct_min,100-year,1pct_plu,500-year
River Rch & RM= Stream0409,Reach-1,1435
     420     677     910     595    1186    2367    1983
Boundary for River Rch & Prof#=Stream0409,Reach-1,1
Up Type=0
Dn Type=3
Dn Slope=0.005
Boundary for River Rch & Prof#=Stream0409,Reach-1,2
Up Type=0
Dn Type=3
Dn Slope=0.005
Boundary for River Rch & Prof#=Stream0409,Reach-1,3
Up Type=0
Dn Type=3
Dn Slope=0.005
Boundary for River Rch & Prof#=Stream0409,Reach-1,4
Up Type=0
Dn Type=3
Dn Slope=0.005
Boundary for River Rch & Prof#=Stream0409,Reach-1,5
Up Type=0
Dn Type=3
Dn Slope=0.005
Boundary for River Rch & Prof#=Stream0409,Reach-1,6
Up Type=0
Dn Type=3
Dn Slope=0.005
Boundary for River Rch & Prof#=Stream0409,Reach-1,7
Up Type=0
Dn Type=3
Dn Slope=0.005

--- Stream0409.g01 (geometry) ---

Geom Title=Existing Conditions

River Reach=Stream0409,Reach-1
Reach XY= 30
      1860025.00     13961625.00      1860056.96     13961624.89
      1860070.37     13961629.63      1860075.45     13961664.55
      1860074.48     13961909.78      1860066.86     13961931.06
      1860035.85     13961965.36      1860027.25     13961980.94
      1860025.51     13962109.78      1860033.14     13962131.05
      1860064.15     13962165.35      1860072.74     13962180.94
      1860076.22     13962364.50      1860083.15     13962381.06
      1860121.30     13962426.60      1860125.41     13962450.00
      1860125.49     13962500.04      1860123.03     13962519.11
      1860114.54     13962534.78      1860033.16     13962618.95
      1860018.85     13962677.17      1859978.67     13962726.59
      1859974.38     13962754.97      1859975.86     13962814.69
      1859991.21     13962842.21      1860026.25     13962871.49
      1860119.07     13962877.23      1860134.74     13962885.62
      1860176.51     13962921.36      1860225.00     13962925.00

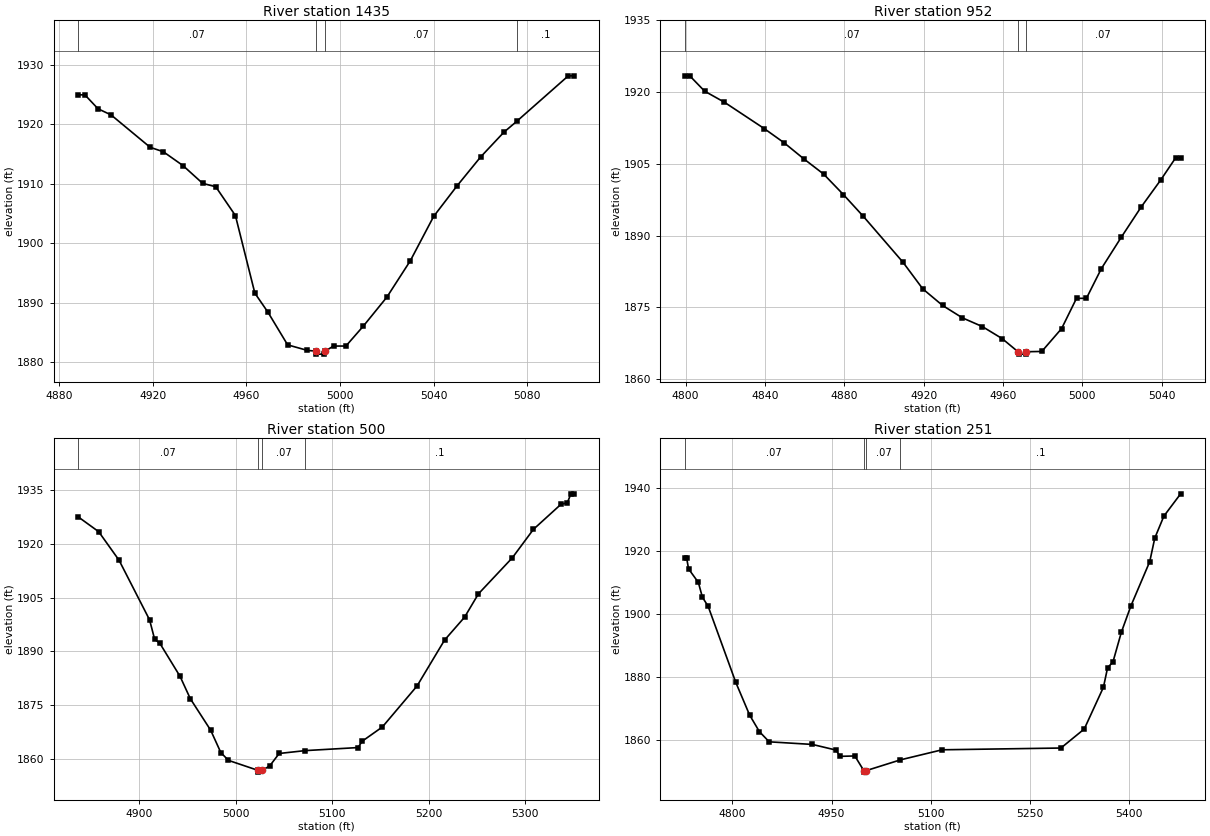
Type RM Length L Ch R = 1,1435,483,483,483
BEGIN DESCRIPTION:
Stream0409 3.0
END DESCRIPTION:
XS GIS Cut Line= 3
      1859975.02     13961725.01      1860075.00     13961775.00
      1860175.02     13961775.00
#Sta/Elev= 30
  4888.2 1924.96  4891.0 1924.96  4896.6 1922.62  4902.2 1921.58  4918.9 1916.13
  4924.5 1915.39  4932.9 1913.06  4941.3 1910.07  4946.9 1909.50  4955.3 1904.65
  4963.6 1891.60  4969.2 1888.39  4977.6 1882.90  4986.0 1881.97  4989.6 1881.84
  4989.8 1881.34  4993.3 1881.34  4993.6 1881.84  4997.2 1882.70  5002.5 1882.70
  5010.0 1886.08  5020.0 1890.93  5030.0 1897.04  5040.0 1904.52  5050.0 1909.66
  5060.0 1914.49  5070.0 1918.68  5075.4 1920.48  5097.5 1928.16  5100.0 1928.16
#Mann=4,-1,0
  4888.2    0.07       0  4989.6    0.05       0  4993.6    0.07       0
  5075.4     0.1       0
Bank Sta=4989.6,4993.6
Exp/Cntr=0.3,0.1

Type RM Length L Ch R = 1,952,452,452,452
BEGIN DESCRIPTION:
Stream0409 2.0
END DESCRIPTION:
XS GIS Cut Line= 3
      1859874.99     13962225.00      1860075.00     13962225.00
      1860124.99     13962225.00
#Sta/Elev= 30
  4799.6 1923.40  4802.1 1923.40  4809.6 1920.19  4819.6 1917.87  4839.6 1912.38
  4849.6 1909.42  4859.6 1906.04  4869.6 1902.85  4879.6 1898.55  4889.6 1894.02
  4909.6 1884.42  4919.6 1878.84  4929.6 1875.37  4939.6 1872.78  4949.6 1870.97
  4959.6 1868.45  4967.6 1865.70  4967.9 1865.20  4971.4 1865.20  4971.6 1865.70
  4979.6 1865.76  4989.6 1870.55  4997.1 1876.87  5002.1 1876.87  5009.6 1883.06
  5019.6 1889.60  5029.6 1895.91  5039.6 1901.64  5047.1 1906.26  5049.6 1906.26
#Mann=3,-1,0
  4799.6    0.07       0  4967.6    0.05       0  4971.6    0.07       0
Bank Sta=4967.6,4971.6
Exp/Cntr=0.3,0.1

Type RM Length L Ch R = 1,500,249,249,249
BEGIN DESCRIPTION:
Stream0409 1.0
END DESCRIPTION:
XS GIS Cut Line= 4
      1859874.98     13962574.99      1860025.00     13962625.00
      1860153.95     13962623.67      1860324.99     13962475.01
#Sta/Elev= 30
  4837.1 1927.48  4858.2 1923.37  4879.3 1915.41  4910.9 1898.80  4916.2 1893.34
  4921.4 1892.32  4942.5 1883.03  4953.1 1876.82  4974.2 1868.03  4984.7 1861.81
  4992.6 1859.62  5023.2 1856.84  5023.5 1856.34  5027.2 1856.84  5035.2 1858.01
  5045.2 1861.54  5072.2 1862.34  5127.0 1863.19  5131.0 1864.92  5152.1 1868.93
  5188.0 1880.35  5216.5 1893.14  5237.3 1899.55  5251.6 1906.04  5286.7 1916.08
  5308.6 1924.03  5337.1 1931.00  5343.7 1931.45  5347.5 1933.93  5350.8 1933.93
#Mann=4,-1,0
  4837.1    0.07       0  5023.2    0.05       0  5027.2    0.07       0
  5072.2     0.1       0
Bank Sta=5023.2,5027.2
Exp/Cntr=0.3,0.1

Type RM Length L Ch R = 1,251,0,0,0
BEGIN DESCRIPTION:
Stream0409 0.0
END DESCRIPTION:
XS GIS Cut Line= 4
      1859775.10     13962726.93      1859972.10     13962865.80
      1860126.04     13962772.95      1860385.91     13962571.36
#Sta/Elev= 30
  4728.1 1917.79  4730.8 1917.79  4733.8 1914.23  4748.6 1909.94  4754.7 1905.25
  4763.4 1902.35  4805.2 1878.20  4826.1 1867.84  4840.9 1862.57  4855.7 1859.34
  4921.0 1858.51  4956.7 1856.72  4962.8 1854.73  4985.2 1854.85  4998.7 1850.22
  4999.0 1849.72  5002.7 1850.22  5053.9 1853.60  5117.2 1856.81  5296.8 1857.37
  5332.1 1863.41  5361.1 1876.67  5367.4 1882.90  5375.4 1884.64  5388.3 1894.21
  5402.7 1902.53  5431.1 1916.54  5438.7 1924.00  5452.5 1930.99  5477.8 1938.06
#Mann=4,-1,0
  4728.1    0.07       0  4998.7    0.05       0  5002.7    0.07       0
  5053.9     0.1       0
Bank Sta=4998.7,5002.7
Exp/Cntr=0.3,0.1

Chan Stop Cuts=-1