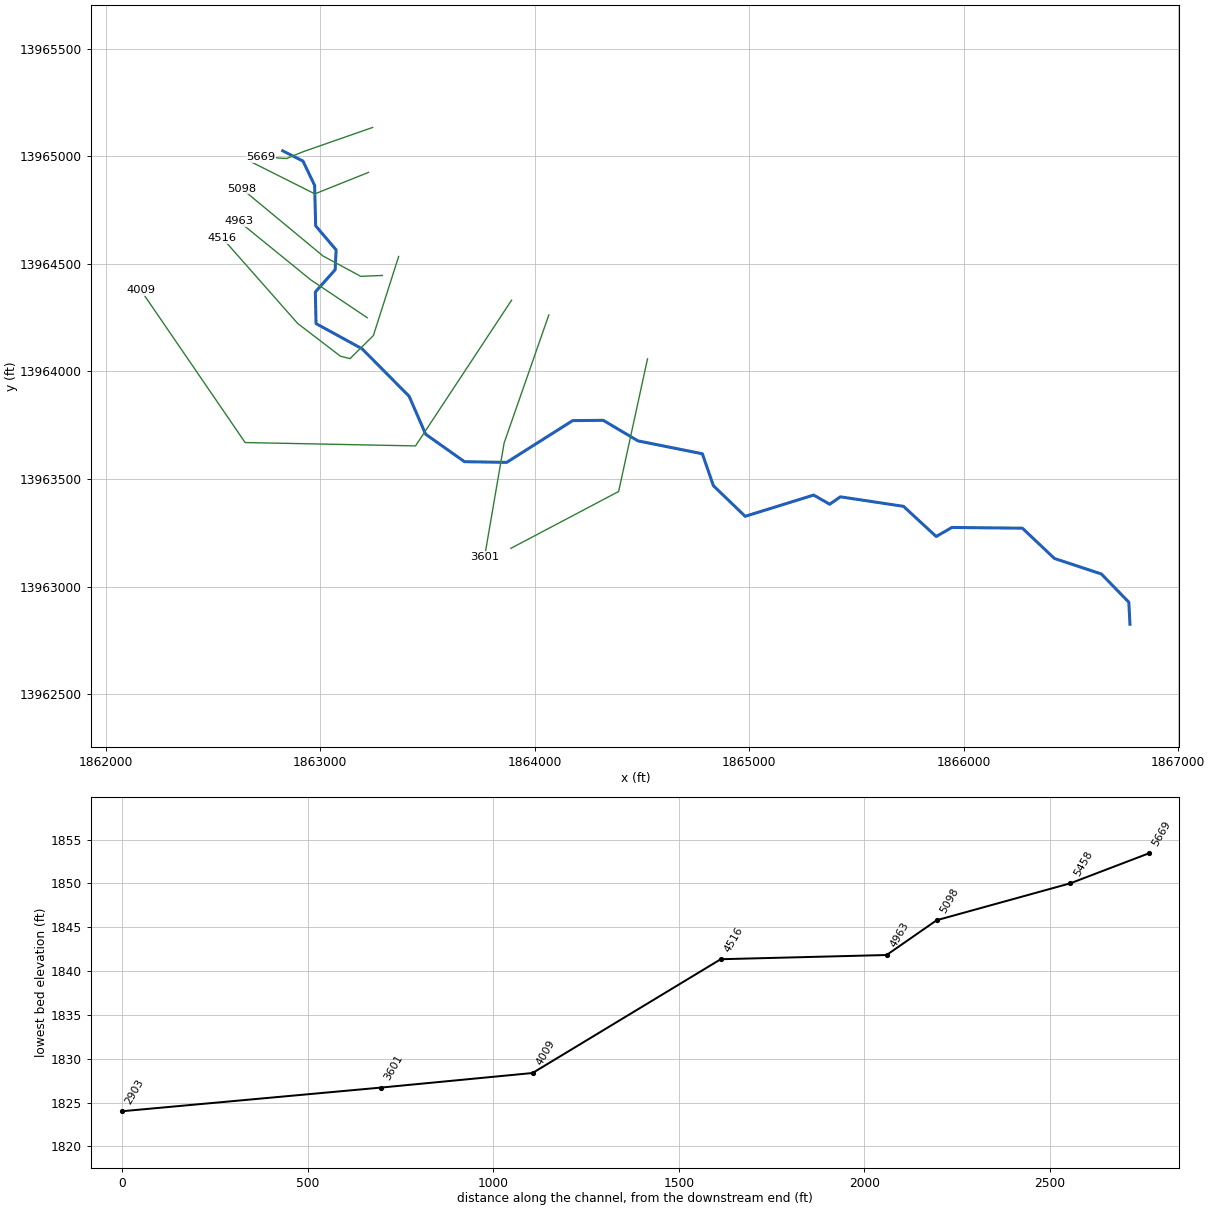
--- Stream0410.prj (project) ---

Proj Title=Stream0410 Base Level Engineering
Current Plan=p01
Default Exp/Contr=0.3,0.1
English Units
Geom File=g01
Flow File=f01
Plan File=p01
BEGIN DESCRIPTION:
Stream0410
END DESCRIPTION:

--- Stream0410.p01 (plan) ---

Plan Title=Multiple Run
Short Identifier=Multiple
Geom File=g01
Flow File=f01
Subcritical Flow
K Sum by GR= 0
Std Step Tol= 0.01
Critical Tol= 0.01
Num of Std Step Trials= 20
Max Error Tol= 0.3
Flow Tol Ratio= 0.001
Split Flow NTrial= 30
Split Flow Tol= 0.02
Split Flow Ratio= 0.02
Log Output Level= 0
Friction Slope Method= 1
Unsteady Friction Slope Method= 2
Unsteady Bridges Friction Slope Method= 1
Parabolic Critical Depth
Global Vel Dist=  1 , 1 , 1
Global Log Level= 0
CheckData=True
Encroach Param= -1, 0, 0, 0
BEGIN DESCRIPTION:
Multiple Run
END DESCRIPTION:

--- Stream0410.f01 (steady flow) ---

Flow Title=Multiple
Number of Profiles=7
Profile Names=10-year,25-year,50-year,1pct_min,100-year,1pct_plu,500-year
River Rch & RM= Stream0410,Reach-1,5669
     875    1471    2030    1356    2706    5398    4742
Boundary for River Rch & Prof#=Stream0410,Reach-1,1
Up Type=0
Dn Type=3
Dn Slope=0.005
Boundary for River Rch & Prof#=Stream0410,Reach-1,2
Up Type=0
Dn Type=3
Dn Slope=0.005
Boundary for River Rch & Prof#=Stream0410,Reach-1,3
Up Type=0
Dn Type=3
Dn Slope=0.005
Boundary for River Rch & Prof#=Stream0410,Reach-1,4
Up Type=0
Dn Type=3
Dn Slope=0.005
Boundary for River Rch & Prof#=Stream0410,Reach-1,5
Up Type=0
Dn Type=3
Dn Slope=0.005
Boundary for River Rch & Prof#=Stream0410,Reach-1,6
Up Type=0
Dn Type=3
Dn Slope=0.005
Boundary for River Rch & Prof#=Stream0410,Reach-1,7
Up Type=0
Dn Type=3
Dn Slope=0.005

--- Stream0410.g01 (geometry) ---

Geom Title=Existing Conditions

River Reach=Stream0410,Reach-1
Reach XY= 30
      1862825.00     13965025.00      1862919.32     13964977.52
      1862973.80     13964864.50      1862978.55     13964676.47
      1863074.06     13964564.51      1863069.59     13964472.58
      1862977.06     13964369.14      1862980.34     13964222.27
      1863194.93     13964105.16      1863414.24     13963884.68
      1863491.49     13963707.95      1863672.55     13963580.47
      1863869.07     13963577.24      1864176.56     13963771.26
      1864319.07     13963772.77      1864480.93     13963677.25
      1864781.50     13963617.27      1864832.86     13963468.83
      1864981.03     13963326.62      1865300.25     13963425.36
      1865375.09     13963382.75      1865424.90     13963417.21
      1865719.15     13963372.94      1865871.58     13963232.79
      1865944.98     13963274.81      1866273.54     13963271.46
      1866422.70     13963130.83      1866641.75     13963058.54
      1866769.65     13962927.50      1866775.00     13962825.00

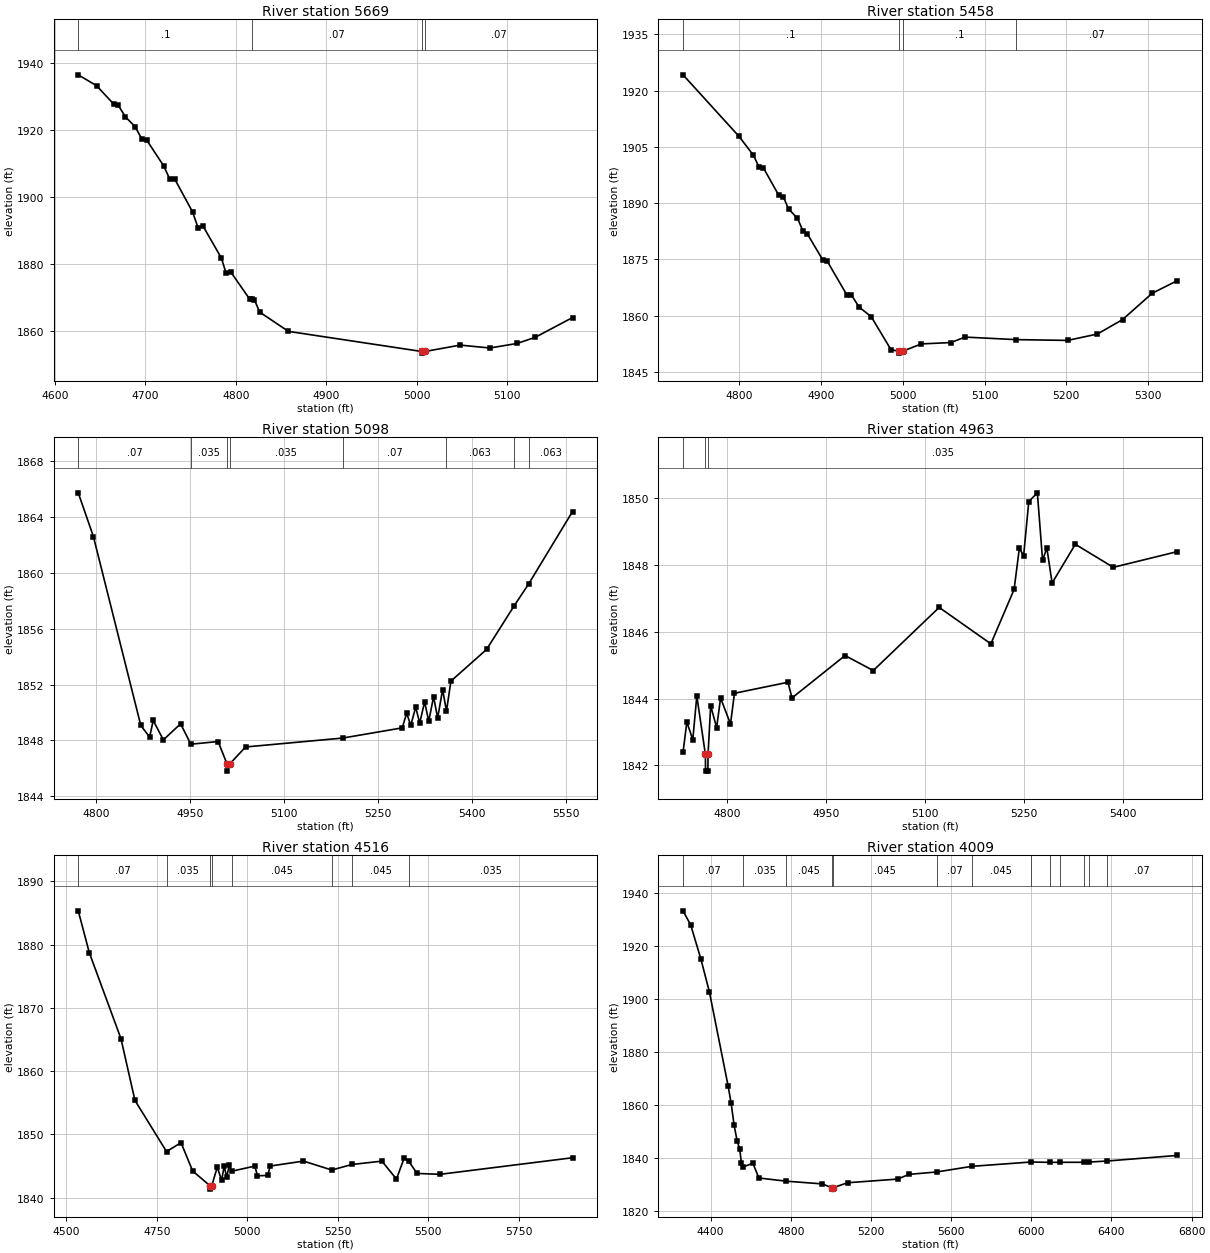
Type RM Length L Ch R = 1,5669,211,211,211
BEGIN DESCRIPTION:
Stream0410 4.0
END DESCRIPTION:
XS GIS Cut Line= 4
      1863244.20     13965133.70      1862920.65     13965021.16
      1862843.27     13964989.51      1862723.74     13964996.54
#Sta/Elev= 30
  4626.0 1936.59  4646.3 1933.32  4665.0 1927.89  4670.3 1927.43  4678.1 1924.02
  4688.7 1921.12  4696.1 1917.45  4701.4 1917.16  4720.4 1909.35  4727.2 1905.36
  4732.5 1905.46  4752.2 1895.64  4758.3 1890.90  4763.6 1891.48  4784.0 1881.87
  4789.4 1877.22  4794.7 1877.57  4815.2 1869.61  4818.3 1869.49  4820.5 1869.40
  4826.3 1865.69  4858.1 1859.92  5005.1 1853.92  5005.3 1853.42  5009.1 1853.92
  5047.9 1855.82  5080.5 1854.95  5110.5 1856.30  5130.6 1858.13  5171.9 1864.05
#Mann=4,-1,0
  4626.0     0.1       0  4818.3    0.07       0  5005.1    0.05       0
  5009.1    0.07       0
Bank Sta=5005.1,5009.1
Exp/Cntr=0.3,0.1

Type RM Length L Ch R = 1,5458,360,360,360
BEGIN DESCRIPTION:
Stream0410 3.0
END DESCRIPTION:
XS GIS Cut Line= 3
      1863224.98     13964924.99      1862975.00     13964825.00
      1862675.04     13964974.98
#Sta/Elev= 30
  4731.2 1924.22  4799.8 1907.78  4817.3 1902.78  4824.1 1899.66  4829.5 1899.43
  4848.3 1892.10  4853.7 1891.76  4860.4 1888.43  4871.2 1885.95  4877.9 1882.62
  4883.3 1881.79  4902.2 1874.85  4907.5 1874.56  4931.8 1865.46  4937.2 1865.49
  4946.6 1862.29  4961.4 1859.73  4985.6 1850.92  4995.7 1850.51  4996.0 1850.01
  4999.7 1850.51  5022.8 1852.47  5059.1 1852.83  5075.9 1854.29  5138.7 1853.61
  5201.7 1853.40  5238.0 1855.10  5268.8 1858.95  5305.1 1865.97  5335.8 1869.34
#Mann=4,-1,0
  4731.2     0.1       0  4995.7    0.05       0  4999.7     0.1       0
  5138.7    0.07       0
Bank Sta=4995.7,4999.7
Exp/Cntr=0.3,0.1

Type RM Length L Ch R = 1,5098,135,135,135
BEGIN DESCRIPTION:
Stream0410 2.0
END DESCRIPTION:
XS GIS Cut Line= 4
      1863289.18     13964445.88      1863188.62     13964441.90
      1863012.99     13964536.39      1862635.09     13964848.35
#Sta/Elev= 30
  4771.0 1865.74  4795.2 1862.61  4871.0 1849.07  4885.1 1848.24  4890.8 1849.43
  4907.0 1848.04  4934.6 1849.19  4951.0 1847.73  4994.6 1847.92  5008.9 1846.30
  5009.1 1845.80  5012.9 1846.30  5038.4 1847.53  5193.9 1848.17  5288.9 1848.90
  5296.0 1849.95  5302.5 1849.08  5310.4 1850.38  5316.8 1849.24  5324.7 1850.77
  5331.2 1849.37  5339.0 1851.13  5345.5 1849.60  5353.4 1851.64  5359.6 1850.11
  5366.7 1852.25  5423.7 1854.52  5467.6 1857.63  5490.9 1859.21  5561.1 1864.40
#Mann=8,-1,0
  4771.0    0.07       0  4951.0   0.035       0  5008.9   0.035       0
  5012.9   0.035       0  5193.9    0.07       0  5359.6   0.063       0
  5467.6    0.07       0  5490.9   0.063       0
Bank Sta=5008.9,5012.9
Exp/Cntr=0.3,0.1

Type RM Length L Ch R = 1,4963,447,447,447
BEGIN DESCRIPTION:
Stream0410 1.0
END DESCRIPTION:
XS GIS Cut Line= 3
      1863219.07     13964249.57      1862956.33     13964425.12
      1862620.27     13964697.39
#Sta/Elev= 30
  4733.2 1842.39  4739.0 1843.30  4748.0 1842.77  4754.1 1844.08  4767.1 1842.33
  4767.3 1841.83  4770.8 1841.83  4771.1 1842.33  4775.1 1843.79  4784.1 1843.13
  4790.1 1844.02  4805.1 1843.24  4811.1 1844.16  4892.2 1844.49  4898.2 1844.02
  4978.6 1845.29  5021.3 1844.84  5121.1 1846.73  5199.4 1845.64  5234.6 1847.27
  5242.5 1848.50  5249.0 1848.28  5256.8 1849.90  5269.8 1850.16  5277.7 1848.14
  5284.2 1848.51  5292.1 1847.46  5327.3 1848.62  5384.8 1847.93  5481.7 1848.40
#Mann=3,-1,0
  4733.2   0.035       0  4767.1   0.035       0  4771.1   0.035       0
Bank Sta=4767.1,4771.1
Exp/Cntr=0.3,0.1

Type RM Length L Ch R = 1,4516,507,507,507
BEGIN DESCRIPTION:
Stream0410 0.0
END DESCRIPTION:
XS GIS Cut Line= 6
      1863365.49     13964534.08      1863247.70     13964166.71
      1863139.00     13964059.51      1863094.02     13964070.74
      1862895.09     13964222.56      1862543.56     13964619.66
#Sta/Elev= 30
  4533.0 1885.33  4563.5 1878.72  4651.0 1865.12  4689.6 1855.37  4776.8 1847.29
  4816.9 1848.69  4849.0 1844.22  4897.6 1841.85  4897.8 1841.35  4901.6 1841.85
  4917.1 1844.84  4929.0 1842.72  4936.1 1844.99  4943.1 1843.24  4950.2 1845.13
  4956.7 1844.18  5020.9 1844.99  5028.0 1843.46  5056.3 1843.51  5063.3 1845.00
  5155.1 1845.78  5233.3 1844.37  5289.4 1845.25  5371.9 1845.77  5412.0 1842.94
  5433.7 1846.31  5446.3 1845.73  5468.9 1843.83  5532.4 1843.69  5898.4 1846.31
#Mann=8,-1,0
  4533.0    0.07       0  4776.8   0.035       0  4897.6   0.045       0
  4901.6   0.035       0  4956.7   0.045       0  5233.3    0.07       0
  5289.4   0.045       0  5446.3   0.035       0
Bank Sta=4897.6,4901.6
Exp/Cntr=0.3,0.1

Type RM Length L Ch R = 1,4009,408,408,408
BEGIN DESCRIPTION:
Stream0410 A
END DESCRIPTION:
XS GIS Cut Line= 4
      1863891.99     13964330.86      1863444.08     13963653.79
      1862649.81     13963669.41      1862163.12     13964378.04
#Sta/Elev= 30
  4262.5 1933.42  4300.9 1928.07  4352.1 1915.10  4394.2 1902.77  4487.5 1867.32
  4502.5 1860.80  4517.6 1852.41  4532.6 1846.53  4545.3 1843.54  4553.7 1838.30
  4560.6 1836.65  4610.9 1838.17  4641.0 1832.57  4778.7 1831.36  4956.9 1830.35
  5006.1 1828.87  5006.3 1828.37  5010.1 1828.87  5083.4 1830.78  5333.4 1832.16
  5389.3 1833.93  5529.5 1834.86  5703.1 1836.97  5997.2 1838.60  6093.0 1838.48
  6144.5 1838.50  6261.3 1838.50  6287.2 1838.58  6378.1 1838.98  6728.4 1841.09
#Mann=13,-1,0
  4262.5    0.07       0  4560.6   0.035       0  4778.7   0.045       0
  5006.1   0.045       0  5010.1   0.045       0  5529.5    0.07       0
  5703.1   0.045       0  5997.2   0.035       0  6093.0    0.07       0
  6144.5   0.035       0  6261.3    0.07       0  6287.2   0.035       0
  6378.1    0.07       0
Bank Sta=5006.1,5010.1
Exp/Cntr=0.3,0.1

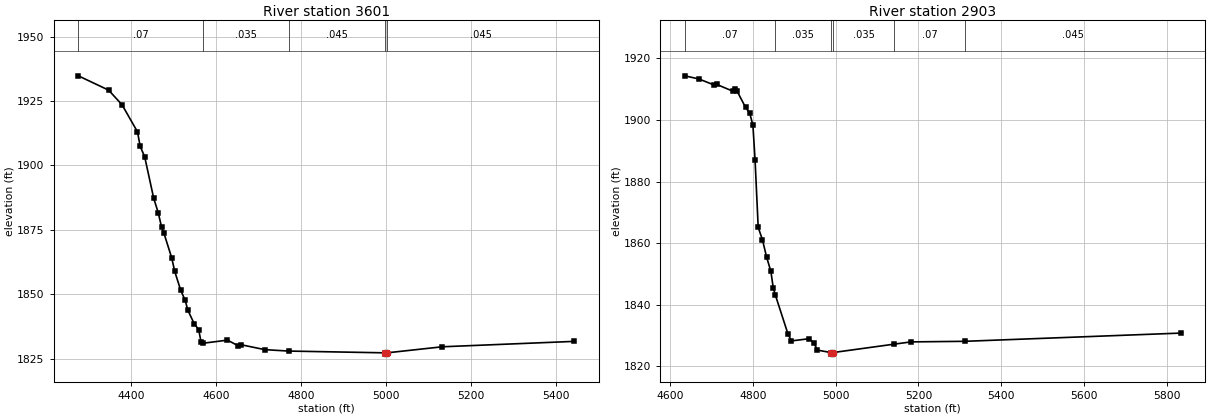
Type RM Length L Ch R = 1,3601,698,698,698
BEGIN DESCRIPTION:
Stream0410 C
END DESCRIPTION:
XS GIS Cut Line= 3
      1864065.61     13964262.30      1863857.28     13963667.68
      1863766.29     13963139.12
#Sta/Elev= 30
  4275.5 1934.75  4346.8 1929.19  4378.3 1923.52  4414.6 1913.03  4421.0 1907.40
  4431.6 1903.31  4452.8 1887.22  4463.4 1881.66  4471.3 1876.03  4476.6 1873.79
  4495.2 1864.07  4502.3 1858.80  4516.3 1851.52  4526.9 1847.56  4533.3 1843.68
  4548.1 1838.52  4558.7 1836.20  4564.3 1831.27  4569.1 1830.94  4626.4 1832.14
  4652.1 1829.90  4657.4 1830.39  4714.1 1828.45  4770.0 1827.90  4997.6 1827.21
  4997.9 1826.71  5001.4 1826.71  5001.6 1827.21  5131.5 1829.56  5441.9 1831.66
#Mann=5,-1,0
  4275.5    0.07       0  4569.1   0.035       0  4770.0   0.045       0
  4997.6   0.045       0  5001.6   0.045       0
Bank Sta=4997.6,5001.6
Exp/Cntr=0.3,0.1

Type RM Length L Ch R = 1,2903,0,0,0
BEGIN DESCRIPTION:
Stream0410 B
END DESCRIPTION:
XS GIS Cut Line= 3
      1864525.67     13964058.28      1864391.13     13963441.98
      1863888.86     13963177.86
#Sta/Elev= 30
  4635.2 1914.36  4669.3 1913.34  4706.9 1911.34  4712.0 1911.59  4750.8 1909.40
  4755.9 1910.05  4761.4 1909.43  4781.9 1904.15  4792.1 1902.22  4799.8 1898.34
  4805.0 1887.08  4812.6 1865.15  4822.8 1861.17  4833.0 1855.47  4843.3 1850.84
  4848.9 1845.58  4854.2 1843.14  4884.2 1830.69  4892.8 1828.30  4935.4 1829.01
  4946.9 1827.71  4955.9 1825.31  4988.8 1824.51  4989.1 1824.01  4992.6 1824.01
  4992.8 1824.51  5141.8 1827.26  5181.9 1827.98  5312.0 1828.17  5833.5 1830.84
#Mann=6,-1,0
  4635.2    0.07       0  4854.2   0.035       0  4988.8   0.035       0
  4992.8   0.035       0  5141.8    0.07       0  5312.0   0.045       0
Bank Sta=4988.8,4992.8
Exp/Cntr=0.3,0.1

Chan Stop Cuts=-1