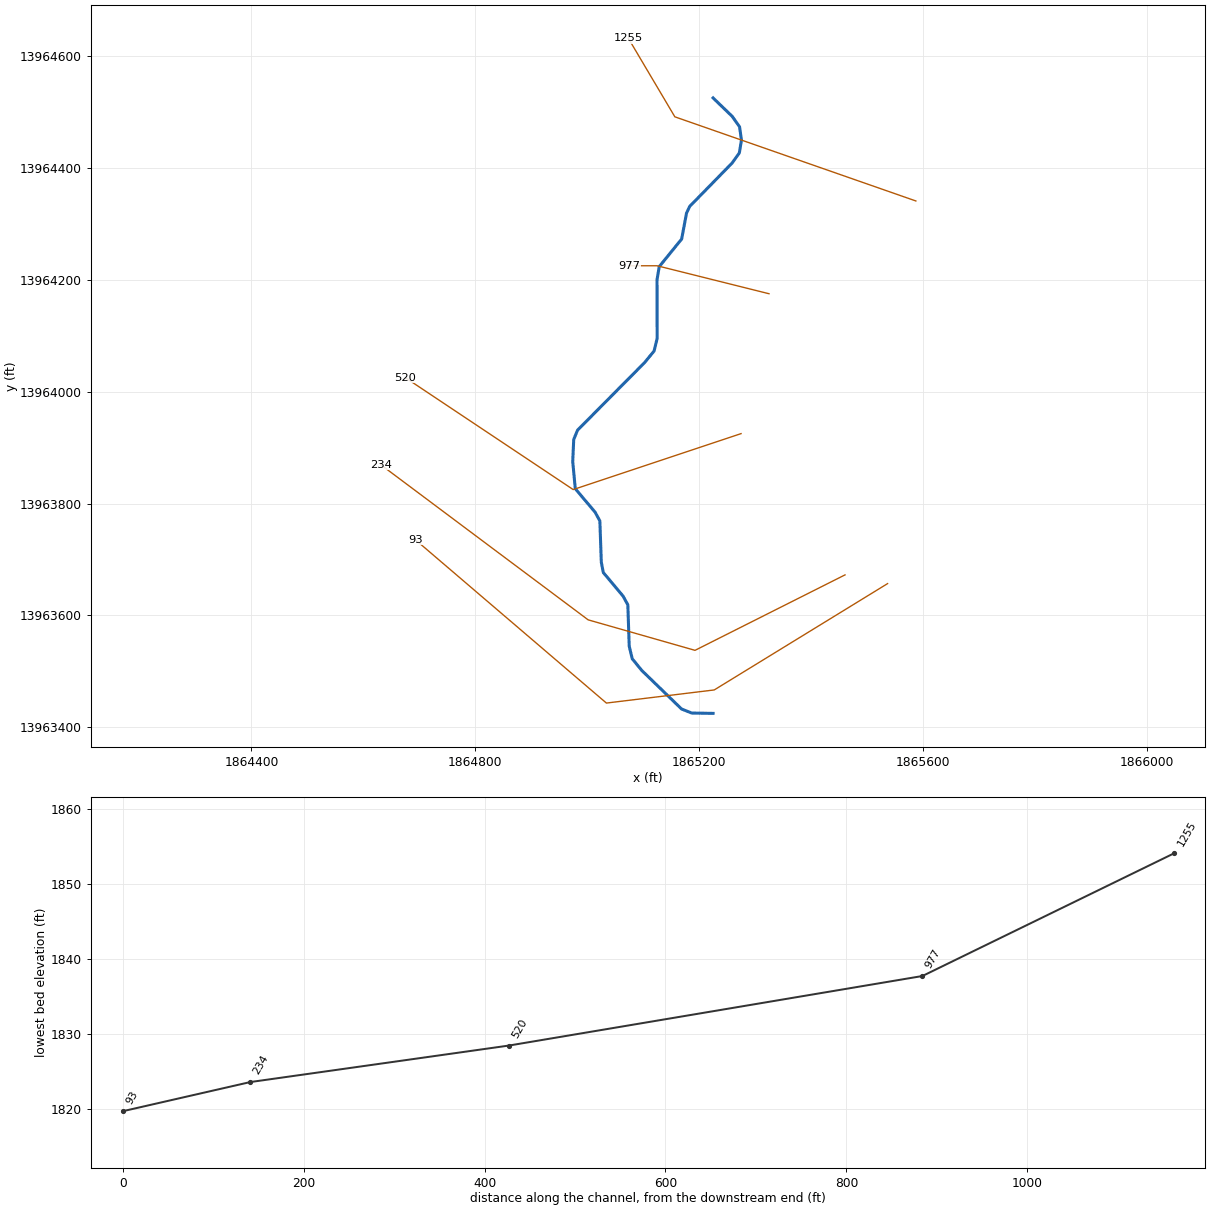
--- Stream0411.prj (project) ---

Proj Title=Stream0411 Base Level Engineering
Current Plan=p01
Default Exp/Contr=0.3,0.1
English Units
Geom File=g01
Flow File=f01
Plan File=p01
Y Axis Title=Elevation
X Axis Title(PF)=Main Channel Distance
X Axis Title(XS)=Station
BEGIN DESCRIPTION:
Stream0411
END DESCRIPTION:
DSS Export Rating Curves= 0
DSS Export Rating Curve Sorted= 0
DSS Export Volume Flow Curves= 0
DXF OffsetX= 0
DXF OffsetY= 0
DXF ScaleX= 1
DXF ScaleY= 10

--- Stream0411.p01 (plan) ---

Plan Title=Multiple Run
Short Identifier=Multiple
Geom File=g01
Flow File=f01
Subcritical Flow
K Sum by GR= 0
Std Step Tol= 0.01
Critical Tol= 0.01
Num of Std Step Trials= 20
Max Error Tol= 0.3
Flow Tol Ratio= 0.001
Split Flow NTrial= 30
Split Flow Tol= 0.02
Split Flow Ratio= 0.02
Log Output Level= 0
Friction Slope Method= 1
Unsteady Friction Slope Method= 2
Unsteady Bridges Friction Slope Method= 1
Parabolic Critical Depth
Global Vel Dist=  1 , 1 , 1
Global Log Level= 0
CheckData=True
Encroach Param= -1, 0, 0, 0
BEGIN DESCRIPTION:
Multiple Run
END DESCRIPTION:

--- Stream0411.f01 (steady flow) ---

Flow Title=Multiple
Number of Profiles=7
Profile Names=10-year,25-year,50-year,1pct_min,100-year,1pct_plu,500-year
River Rch & RM= Stream0411,Reach-1,1255
     568     934    1271     840    1675    3342    2866
River Rch & RM= Stream0411,Reach-1,93
    1259    2164    3030    2050    4090    8161    7364
Boundary for River Rch & Prof#=Stream0411,Reach-1,1
Up Type=0
Dn Type=3
Dn Slope=0.005
Boundary for River Rch & Prof#=Stream0411,Reach-1,2
Up Type=0
Dn Type=3
Dn Slope=0.005
Boundary for River Rch & Prof#=Stream0411,Reach-1,3
Up Type=0
Dn Type=3
Dn Slope=0.005
Boundary for River Rch & Prof#=Stream0411,Reach-1,4
Up Type=0
Dn Type=3
Dn Slope=0.005
Boundary for River Rch & Prof#=Stream0411,Reach-1,5
Up Type=0
Dn Type=3
Dn Slope=0.005
Boundary for River Rch & Prof#=Stream0411,Reach-1,6
Up Type=0
Dn Type=3
Dn Slope=0.005
Boundary for River Rch & Prof#=Stream0411,Reach-1,7
Up Type=0
Dn Type=3
Dn Slope=0.005

--- Stream0411.g01 (geometry) ---

Geom Title=Existing Conditions
Program Version=4.10

River Reach=Stream0411      ,Reach-1
Reach XY= 30
        1865225.       13964525.      1865259.26     13964491.92
      1865272.33     13964473.38      1865275.72      13964449.9
      1865271.91     13964426.58      1865258.73     13964408.32
      1865183.16     13964331.05      1865177.51     13964318.96
      1865168.86     13964272.83      1865128.76     13964223.44
      1865124.81     13964200.08      1865125.02     13964094.99
      1865119.53     13964072.55      1865102.14     13964051.47
      1864982.76     13963931.17      1864975.93     13963914.52
      1864974.15     13963875.01       1864978.7      13963826.6
       1865014.1     13963784.63      1865022.64     13963769.03
      1865025.24      13963695.1      1865028.85      13963676.6
      1865064.11     13963634.63      1865072.64     13963619.02
      1865075.12     13963545.05      1865080.51     13963522.56
      1865097.84     13963501.43      1865168.76     13963432.75
      1865186.83     13963425.59        1865225.       13963425.

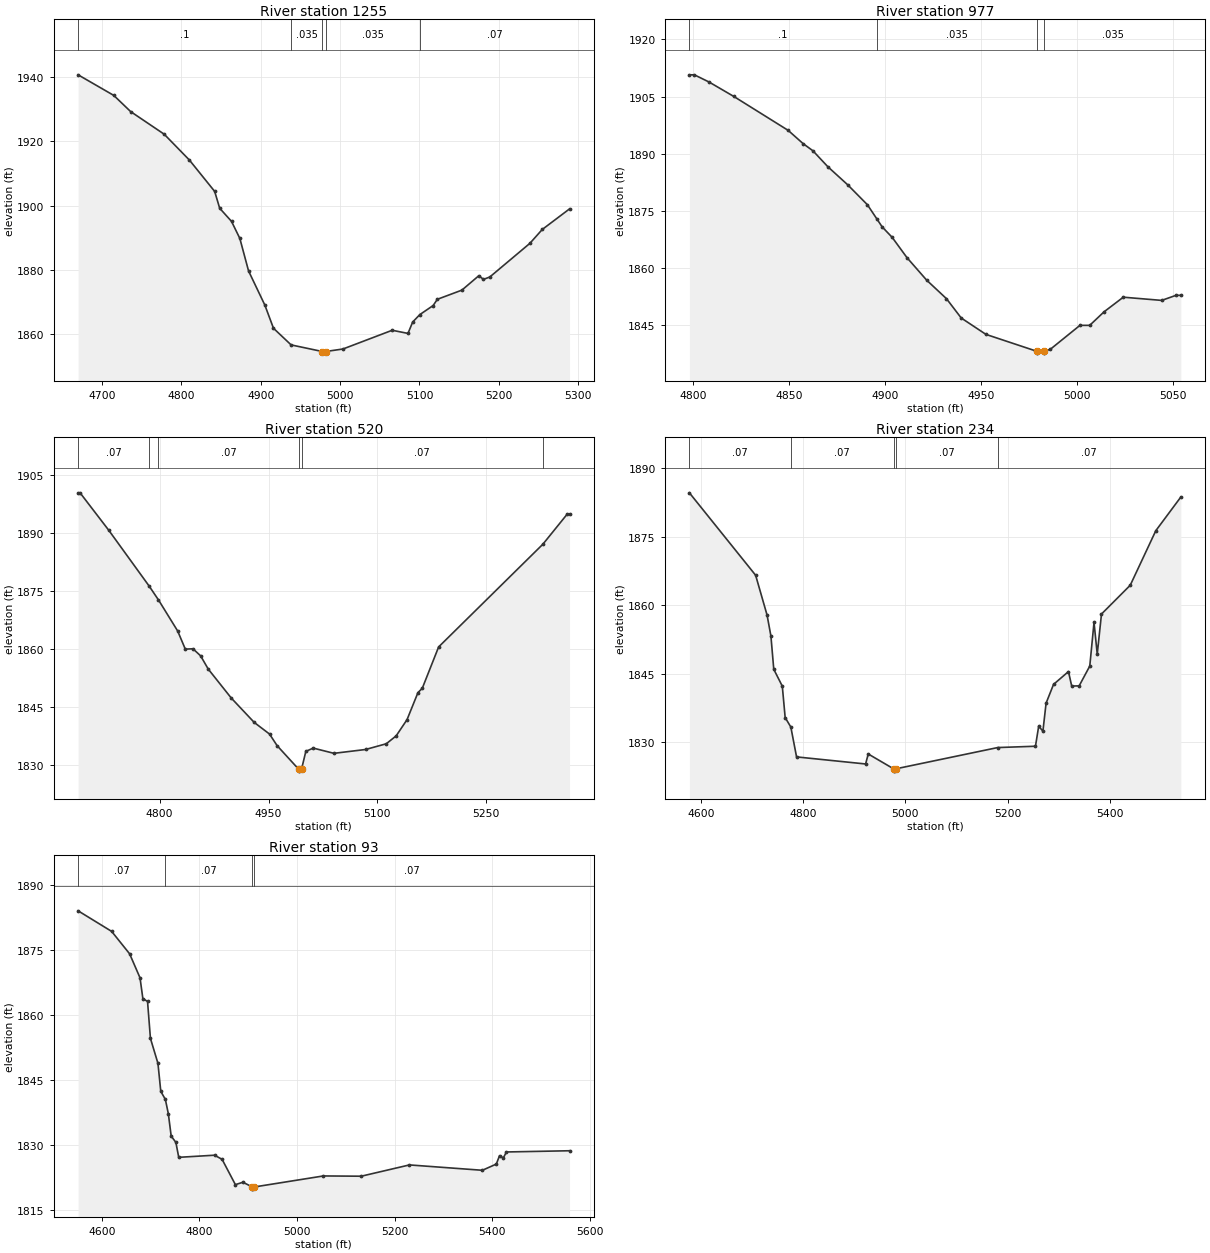
Type RM Length L Ch R = 1 ,1255    ,278,278,278
BEGIN DESCRIPTION:
Stream0411 3.0
END DESCRIPTION:
XS GIS Cut Line= 3
      1865587.46     13964340.82      1865156.67     13964491.22
      1865073.61     13964631.49
#Sta/Elev= 30
  4669.8 1940.65  4714.8 1934.24    4736 1929.22  4778.3 1922.18  4810.1 1914.13
  4841.9 1904.39  4848.2 1899.16  4863.1 1895.08  4873.6 1889.77  4884.6 1879.65
  4905.1 1869.05    4916 1861.83  4938.2 1856.66  4977.6  1854.6  4977.8  1854.1
  4981.6  1854.6  5003.5 1855.38  5065.6 1861.21  5085.5 1860.23  5091.4 1863.77
  5100.4 1866.08  5117.2  1868.9  5122.5 1870.84  5153.4 1873.69  5174.8 1878.18
  5180.6 1877.03  5188.6 1877.78  5239.1 1888.24  5254.7 1892.56  5289.1 1898.96
#Mann= 5 ,-1 , 0
  4669.8      .1       0  4938.2    .035       0  4977.6    .035       0
  4981.6    .035       0  5100.4     .07       0
Bank Sta=4977.6,4981.6
XS Rating Curve= 0 ,0
Exp/Cntr=0.3,0.1

Type RM Length L Ch R = 1 ,977     ,457,457,457
BEGIN DESCRIPTION:
Stream0411 2.0
END DESCRIPTION:
XS GIS Cut Line= 3
        1865325.       13964175.        1865125.       13964225.
      1865074.96       13964225.
#Sta/Elev= 30
    4798 1910.69  4800.6 1910.69  4808.3 1908.79  4821.2 1905.01  4849.5 1896.13
  4857.3 1892.65  4862.4 1890.78  4870.2 1886.59  4880.5 1881.88  4890.8 1876.64
  4895.6 1873.02  4898.5 1870.83  4903.7  1868.1  4911.4 1862.79  4921.7 1856.87
    4932 1852.03  4939.7 1846.96  4952.6 1842.66    4979 1838.25  4979.2 1837.75
  4982.7 1837.75    4983 1838.25  4986.1 1838.73  5001.6 1845.03  5006.7 1845.03
  5014.2 1848.59  5024.2 1852.41  5044.2 1851.57  5051.7  1852.9  5054.2  1852.9
#Mann= 4 ,-1 , 0
    4798      .1       0  4895.6    .035       0    4979    .035       0
    4983    .035       0
Bank Sta=4979,4983
XS Rating Curve= 0 ,0
Exp/Cntr=0.3,0.1

Type RM Length L Ch R = 1 ,520     ,286,286,286
BEGIN DESCRIPTION:
Stream0411 1.0
END DESCRIPTION:
XS GIS Cut Line= 3
      1865275.04     13963925.01        1864975.       13963825.
      1864675.02     13964024.99
#Sta/Elev= 30
  4687.8 1900.39  4690.5 1900.39    4730 1890.72  4785.6  1876.3  4798.5 1872.71
  4824.9 1864.69  4835.4 1860.01    4846 1860.09  4856.5 1858.27    4867 1854.85
  4898.7 1847.37  4930.3 1841.07  4951.4 1838.06  4961.9 1835.05  4991.5 1828.98
  4991.8 1828.48  4995.5 1828.98  5001.4 1833.58  5011.6 1834.43  5040.1 1833.08
  5083.7 1834.07  5112.2 1835.55  5125.8 1837.59  5140.8 1841.79  5155.8 1848.76
  5161.8  1849.9  5184.3 1860.57  5327.9 1887.12  5361.6 1894.94  5364.6 1894.94
#Mann= 6 ,-1 , 0
  4687.8     .07       0  4785.6    .035       0  4798.5     .07       0
  4991.5     .05       0  4995.5     .07       0  5327.9    .035       0
Bank Sta=4991.5,4995.5
XS Rating Curve= 0 ,0
Exp/Cntr=0.3,0.1

Type RM Length L Ch R = 1 ,234     ,141,141,141
BEGIN DESCRIPTION:
Stream0411 0.0
END DESCRIPTION:
XS GIS Cut Line= 4
      1865460.78     13963672.52      1865192.72     13963537.66
       1865001.7     13963592.18      1864630.95     13963869.47
#Sta/Elev= 30
  4577.4 1884.66    4707 1866.58  4729.4 1857.84  4736.9 1853.26  4742.5 1845.95
  4759.2 1842.25  4764.8 1835.36  4775.9 1833.28  4787.1 1826.73  4922.2 1825.18
  4927.4 1827.37  4977.1 1824.11  4977.3 1823.61  4981.1 1824.11  5180.7 1828.78
  5254.6 1829.07  5260.9 1833.45  5269.2 1832.39  5275.4 1838.52    5290 1842.64
  5319.2 1845.45  5325.5 1842.28  5340.1 1842.31  5360.9 1846.66  5369.2 1856.23
  5375.5 1849.27  5383.8 1858.07  5440.1 1864.39  5490.1 1876.35  5539.1 1883.74
#Mann= 5 ,-1 , 0
  4577.4     .07       0  4775.9     .07       0  4977.1     .05       0
  4981.1     .07       0  5180.7     .07       0
Bank Sta=4977.1,4981.1
XS Rating Curve= 0 ,0
Exp/Cntr=0.3,0.1

Type RM Length L Ch R = 1 ,93      ,0,0,0
BEGIN DESCRIPTION:
Stream0411 0.1
END DESCRIPTION:
XS GIS Cut Line= 4
      1865536.93     13963656.97      1865227.05     13963466.87
      1865034.34     13963443.43       1864693.2      13963735.1
#Sta/Elev= 30
  4551.6 1884.12  4620.3 1879.36  4657.1 1874.17  4678.4 1868.61  4684.2 1863.82
  4693.8 1863.14  4699.7 1854.61  4715.1 1848.83  4720.9 1842.35  4730.3 1840.48
  4736.4 1837.16  4742.2    1832  4751.8 1830.54  4757.7 1827.08  4831.1 1827.57
  4846.5 1826.61  4873.7 1820.76  4889.1 1821.31  4908.4 1820.22  4908.7 1819.72
  4912.4 1820.22    5054 1822.77  5131.5 1822.71  5230.2 1825.32  5379.5 1824.08
  5408.1 1825.52  5414.7 1827.47  5422.4 1826.94  5428.9 1828.32  5558.1  1828.6
#Mann= 4 ,-1 , 0
  4551.6     .07       0  4730.3     .07       0  4908.4     .05       0
  4912.4     .07       0
Bank Sta=4908.4,4912.4
XS Rating Curve= 0 ,0
Exp/Cntr=0.3,0.1

Chan Stop Cuts=-1
Use User Specified Reach Order=0
Composite Channel Slope=5