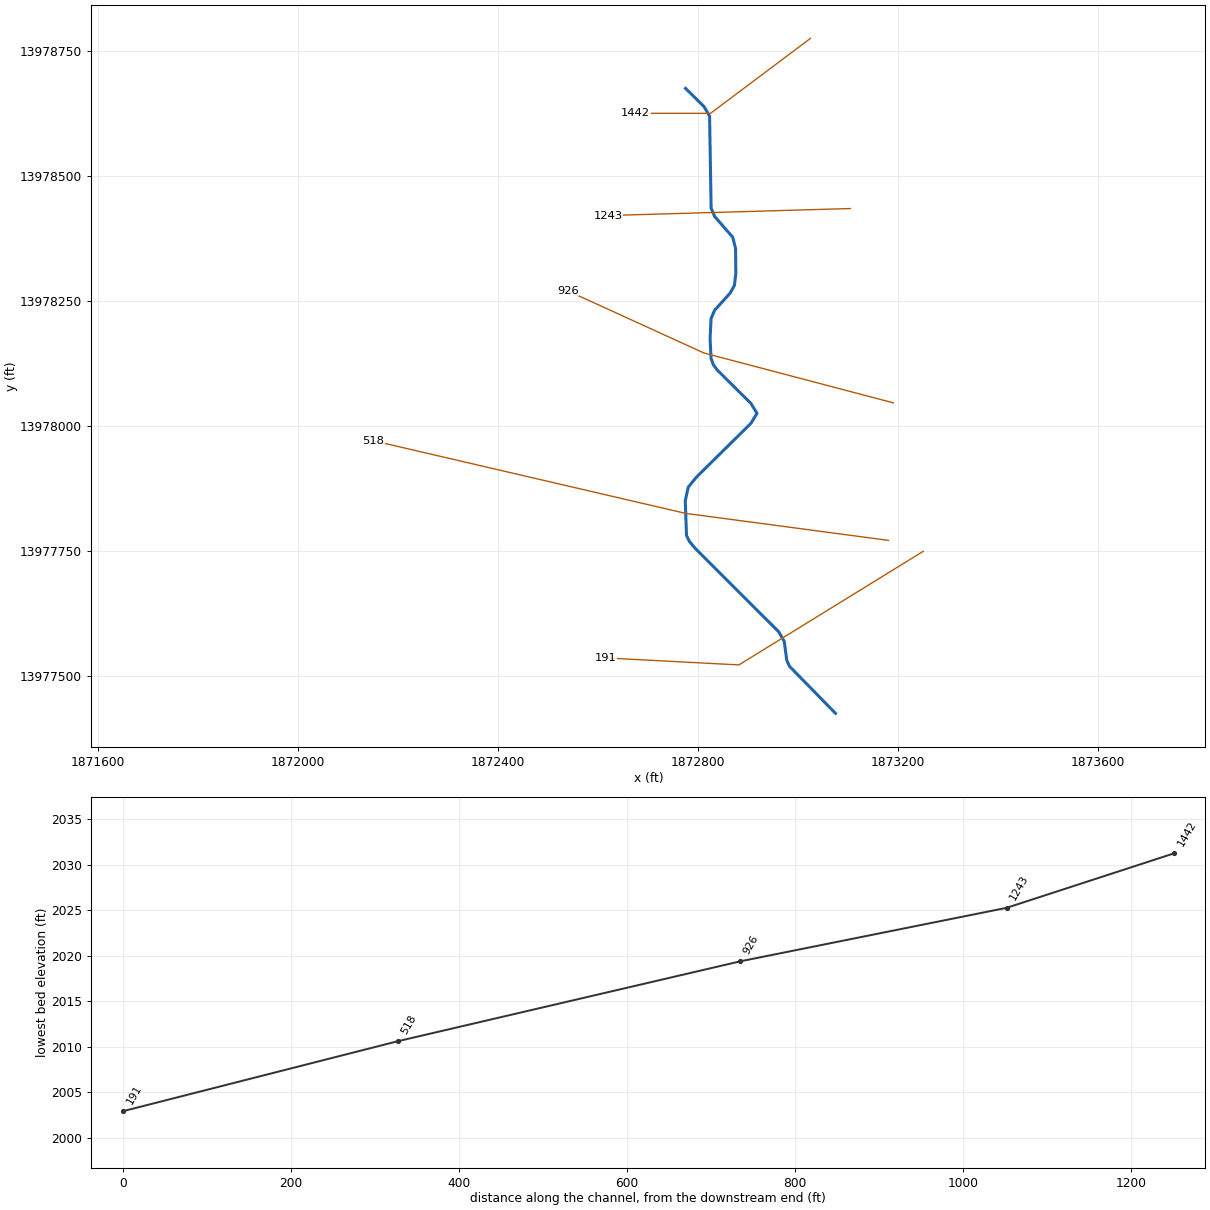
--- Stream0413.prj (project) ---

Proj Title=Stream0413 Base Level Engineering
Current Plan=p01
Default Exp/Contr=0.3,0.1
English Units
Geom File=g01
Flow File=f01
Plan File=p01
BEGIN DESCRIPTION:
Stream0413
END DESCRIPTION:

--- Stream0413.p01 (plan) ---

Plan Title=Multiple Run
Short Identifier=Multiple
Geom File=g01
Flow File=f01
Subcritical Flow
K Sum by GR= 0
Std Step Tol= 0.01
Critical Tol= 0.01
Num of Std Step Trials= 20
Max Error Tol= 0.3
Flow Tol Ratio= 0.001
Split Flow NTrial= 30
Split Flow Tol= 0.02
Split Flow Ratio= 0.02
Log Output Level= 0
Friction Slope Method= 1
Unsteady Friction Slope Method= 2
Unsteady Bridges Friction Slope Method= 1
Parabolic Critical Depth
Global Vel Dist=  1 , 1 , 1
Global Log Level= 0
CheckData=True
Encroach Param= -1, 0, 0, 0
BEGIN DESCRIPTION:
Multiple Run
END DESCRIPTION:

--- Stream0413.f01 (steady flow) ---

Flow Title=Multiple
Number of Profiles=7
Profile Names=10-year,25-year,50-year,1pct_min,100-year,1pct_plu,500-year
River Rch & RM= Stream0413,Reach-1,1442
     586     961    1305     859    1715    3421    2919
Boundary for River Rch & Prof#=Stream0413,Reach-1,1
Up Type=0
Dn Type=3
Dn Slope=0.005
Boundary for River Rch & Prof#=Stream0413,Reach-1,2
Up Type=0
Dn Type=3
Dn Slope=0.005
Boundary for River Rch & Prof#=Stream0413,Reach-1,3
Up Type=0
Dn Type=3
Dn Slope=0.005
Boundary for River Rch & Prof#=Stream0413,Reach-1,4
Up Type=0
Dn Type=3
Dn Slope=0.005
Boundary for River Rch & Prof#=Stream0413,Reach-1,5
Up Type=0
Dn Type=3
Dn Slope=0.005
Boundary for River Rch & Prof#=Stream0413,Reach-1,6
Up Type=0
Dn Type=3
Dn Slope=0.005
Boundary for River Rch & Prof#=Stream0413,Reach-1,7
Up Type=0
Dn Type=3
Dn Slope=0.005

--- Stream0413.g01 (geometry) ---

Geom Title=Existing Conditions

River Reach=Stream0413,Reach-1
Reach XY= 30
      1872775.00     13978675.00      1872812.08     13978638.50
      1872823.11     13978619.22      1872826.22     13978435.50
      1872833.15     13978418.94      1872869.32     13978377.31
      1872875.09     13978354.90      1872875.59     13978304.95
      1872872.83     13978280.97      1872864.18     13978265.37
      1872833.09     13978231.04      1872826.10     13978214.45
      1872824.15     13978174.99      1872825.95     13978135.48
      1872830.43     13978122.57      1872838.40     13978111.70
      1872905.75     13978044.98      1872917.92     13978025.00
      1872905.79     13978005.00      1872797.84     13977898.52
      1872780.40     13977877.43      1872774.49     13977850.04
      1872776.96     13977780.89      1872782.76     13977768.83
      1872794.58     13977754.85      1872961.37     13977588.21
      1872972.48     13977568.96      1872977.52     13977531.04
      1872983.11     13977518.93      1873075.00     13977425.00

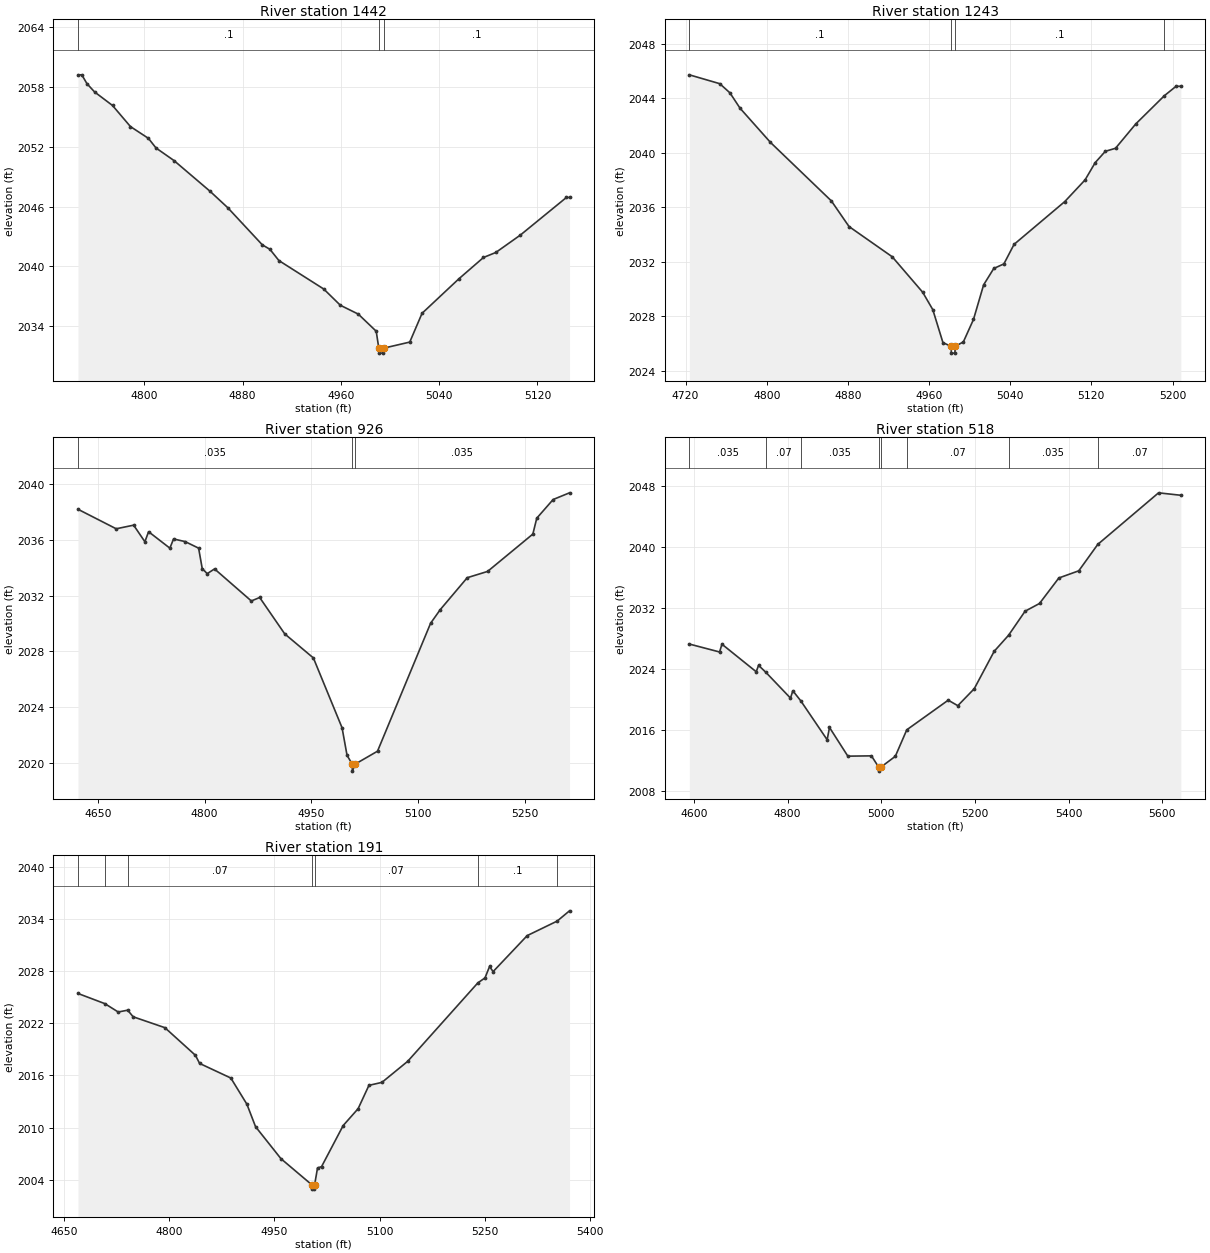
Type RM Length L Ch R = 1,1442,199,199,199
BEGIN DESCRIPTION:
Stream0413 3.0
END DESCRIPTION:
XS GIS Cut Line= 3
      1873024.98     13978774.98      1872825.00     13978625.00
      1872674.97     13978625.00
#Sta/Elev= 30
  4746.1 2059.23  4749.2 2059.23  4753.4 2058.34  4759.6 2057.51  4774.2 2056.15
  4788.8 2054.03  4803.4 2052.85  4809.6 2051.88  4824.2 2050.62  4853.4 2047.55
  4867.9 2045.89  4896.1 2042.15  4902.3 2041.70  4909.6 2040.57  4946.1 2037.71
  4959.6 2036.08  4974.2 2035.19  4988.8 2033.47  4990.9 2031.77  4991.2 2031.27
  4994.7 2031.27  4994.9 2031.77  5016.1 2032.38  5026.1 2035.27  5056.1 2038.74
  5076.1 2040.88  5086.1 2041.38  5106.1 2043.13  5143.6 2046.91  5146.1 2046.91
#Mann=3,-1,0
  4746.1     0.1       0  4990.9    0.05       0  4994.9     0.1       0
Bank Sta=4990.9,4994.9
Exp/Cntr=0.3,0.1

Type RM Length L Ch R = 1,1243,317,317,317
BEGIN DESCRIPTION:
Stream0413 4.0
END DESCRIPTION:
XS GIS Cut Line= 2
      1873104.94     13978434.60      1872620.64     13978420.65
#Sta/Elev= 30
  4723.7 2045.71  4753.7 2045.06  4763.7 2044.39  4773.7 2043.26  4803.7 2040.75
  4863.7 2036.46  4881.1 2034.58  4923.7 2032.36  4953.7 2029.76  4963.7 2028.48
  4973.7 2026.06  4981.7 2025.79  4982.0 2025.29  4985.5 2025.29  4985.7 2025.79
  4993.8 2026.11  5003.8 2027.76  5013.8 2030.30  5023.8 2031.50  5033.8 2031.84
  5043.8 2033.27  5093.8 2036.41  5113.8 2038.00  5123.8 2039.27  5133.8 2040.10
  5143.8 2040.32  5163.8 2042.11  5192.0 2044.18  5203.5 2044.87  5208.2 2044.87
#Mann=4,-1,0
  4723.7     0.1       0  4981.7    0.05       0  4985.7     0.1       0
  5192.0    0.07       0
Bank Sta=4981.7,4985.7
Exp/Cntr=0.3,0.1

Type RM Length L Ch R = 1,926,408,408,408
BEGIN DESCRIPTION:
Stream0413 2.0
END DESCRIPTION:
XS GIS Cut Line= 3
      1873190.62     13978046.01      1872811.97     13978145.65
      1872539.83     13978269.89
#Sta/Elev= 30
  4622.0 2038.20  4675.7 2036.80  4700.2 2037.06  4716.0 2035.87  4721.2 2036.59
  4751.1 2035.41  4756.3 2036.07  4772.6 2035.88  4791.5 2035.41  4796.6 2033.94
  4803.6 2033.58  4813.9 2033.92  4865.6 2031.62  4877.3 2031.87  4912.5 2029.26
  4952.8 2027.53  4993.1 2022.52  5000.1 2020.54  5007.4 2019.91  5007.6 2019.41
  5011.4 2019.91  5042.9 2020.84  5117.5 2030.02  5131.1 2031.00  5169.0 2033.29
  5197.6 2033.74  5261.2 2036.42  5266.7 2037.56  5289.7 2038.90  5312.7 2039.38
#Mann=3,-1,0
  4622.0   0.035       0  5007.4   0.035       0  5011.4   0.035       0
Bank Sta=5007.4,5011.4
Exp/Cntr=0.3,0.1

Type RM Length L Ch R = 1,518,327,327,327
BEGIN DESCRIPTION:
Stream0413 1.0
END DESCRIPTION:
XS GIS Cut Line= 3
      1873180.64     13977771.01      1872775.00     13977825.00
      1872150.97     13977970.15
#Sta/Elev= 30
  4589.9 2027.26  4654.5 2026.22  4659.6 2027.24  4732.8 2023.63  4737.8 2024.47
  4753.5 2023.55  4806.0 2020.18  4811.0 2021.14  4827.9 2019.83  4884.3 2014.73
  4889.3 2016.34  4928.5 2012.58  4978.9 2012.62  4994.6 2011.12  4994.8 2010.62
  4998.6 2011.12  5029.9 2012.56  5054.4 2016.03  5142.9 2019.91  5163.4 2019.19
  5198.5 2021.41  5241.1 2026.31  5271.8 2028.41  5307.1 2031.56  5337.9 2032.57
  5379.2 2035.91  5421.8 2036.85  5462.4 2040.31  5592.2 2047.06  5639.8 2046.74
#Mann=8,-1,0
  4589.9   0.035       0  4753.5    0.07       0  4827.9   0.035       0
  4994.6   0.035       0  4998.6   0.035       0  5054.4    0.07       0
  5271.8   0.035       0  5462.4    0.07       0
Bank Sta=4994.6,4998.6
Exp/Cntr=0.3,0.1

Type RM Length L Ch R = 1,191,0,0,0
BEGIN DESCRIPTION:
Stream0413 0.0
END DESCRIPTION:
XS GIS Cut Line= 3
      1873250.39     13977749.10      1872881.72     13977521.92
      1872614.73     13977535.87
#Sta/Elev= 30
  4670.3 2025.42  4708.6 2024.25  4727.6 2023.29  4741.1 2023.50  4748.9 2022.74
  4794.1 2021.49  4837.7 2018.31  4843.6 2017.38  4888.1 2015.70  4911.0 2012.69
  4923.3 2010.11  4959.5 2006.43  5003.5 2003.43  5003.8 2002.93  5007.3 2002.93
  5007.5 2003.43  5011.6 2005.35  5017.4 2005.52  5048.2 2010.24  5069.5 2012.18
  5084.9 2014.86  5103.4 2015.20  5140.1 2017.62  5240.1 2026.64  5250.3 2027.21
  5256.8 2028.53  5261.8 2027.93  5310.4 2032.07  5353.1 2033.74  5370.7 2034.92
#Mann=7,-1,0
  4670.3   0.063       0  4708.6   0.035       0  4741.1    0.07       0
  5003.5    0.05       0  5007.5    0.07       0  5240.1     0.1       0
  5353.1    0.07       0
Bank Sta=5003.5,5007.5
Exp/Cntr=0.3,0.1

Chan Stop Cuts=-1