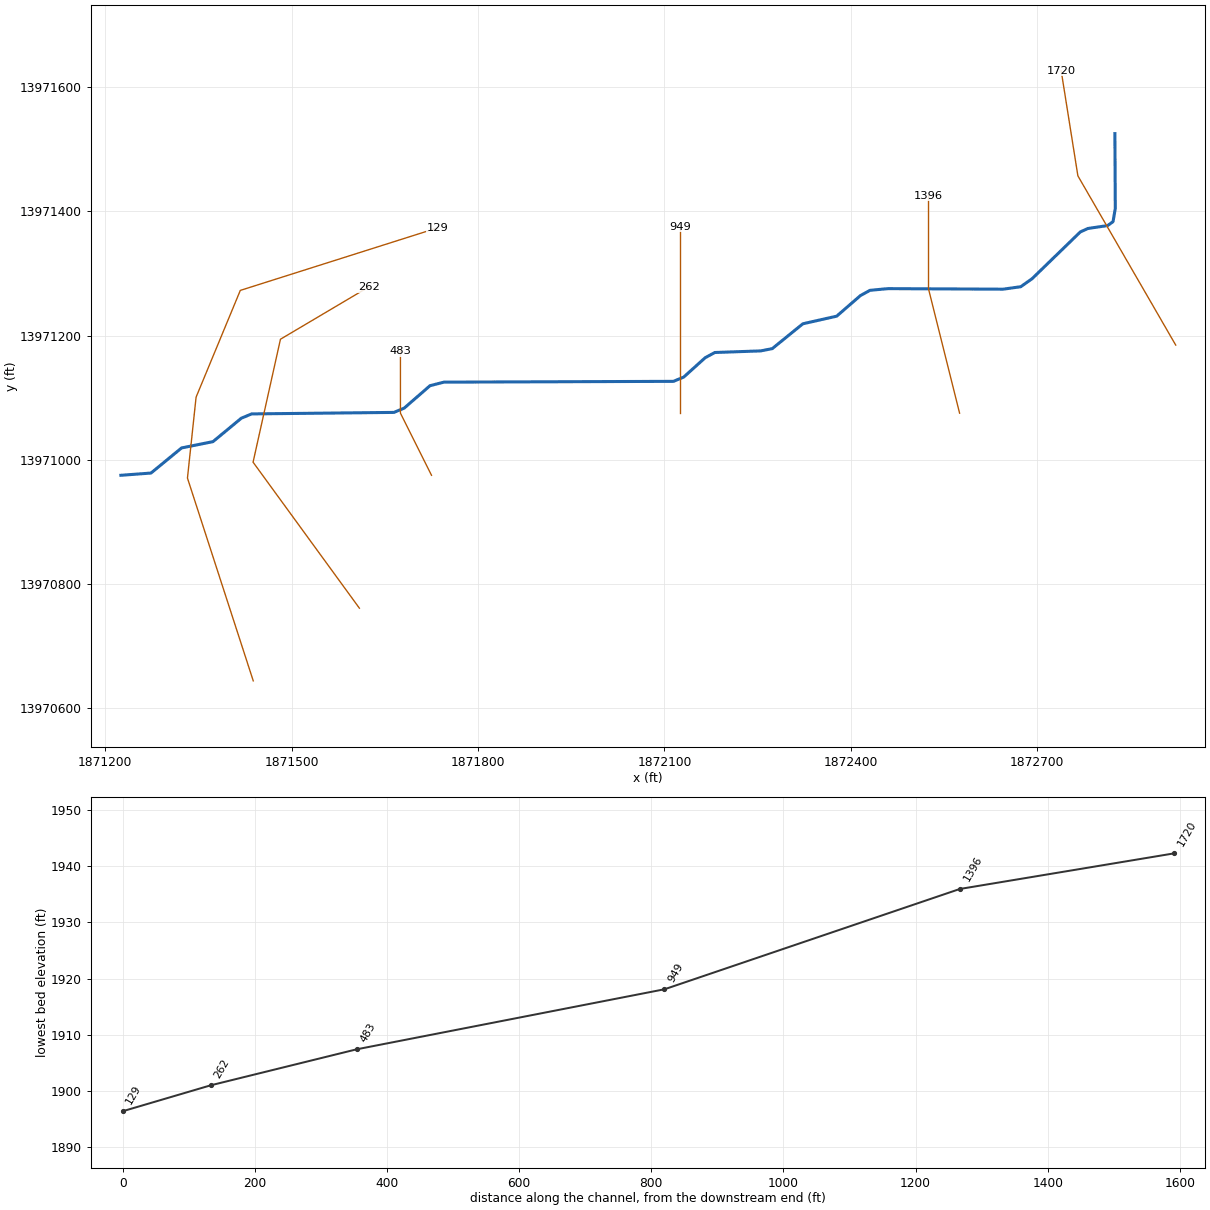
--- Stream0416.prj (project) ---

Proj Title=Stream0416 Base Level Engineering
Current Plan=p01
Default Exp/Contr=0.3,0.1
English Units
Geom File=g01
Flow File=f01
Plan File=p01
BEGIN DESCRIPTION:
Stream0416
END DESCRIPTION:

--- Stream0416.p01 (plan) ---

Plan Title=Multiple Run
Short Identifier=Multiple
Geom File=g01
Flow File=f01
Subcritical Flow
K Sum by GR= 0
Std Step Tol= 0.01
Critical Tol= 0.01
Num of Std Step Trials= 20
Max Error Tol= 0.3
Flow Tol Ratio= 0.001
Split Flow NTrial= 30
Split Flow Tol= 0.02
Split Flow Ratio= 0.02
Log Output Level= 0
Friction Slope Method= 1
Unsteady Friction Slope Method= 2
Unsteady Bridges Friction Slope Method= 1
Parabolic Critical Depth
Global Vel Dist=  1 , 1 , 1
Global Log Level= 0
CheckData=True
Encroach Param= -1, 0, 0, 0
BEGIN DESCRIPTION:
Multiple Run
END DESCRIPTION:

--- Stream0416.f01 (steady flow) ---

Flow Title=Multiple
Number of Profiles=7
Profile Names=10-year,25-year,50-year,1pct_min,100-year,1pct_plu,500-year
River Rch & RM= Stream0416,Reach-1,1720
     610    1007    1374     909    1815    3620    3119
Boundary for River Rch & Prof#=Stream0416,Reach-1,1
Up Type=0
Dn Type=3
Dn Slope=0.005
Boundary for River Rch & Prof#=Stream0416,Reach-1,2
Up Type=0
Dn Type=3
Dn Slope=0.005
Boundary for River Rch & Prof#=Stream0416,Reach-1,3
Up Type=0
Dn Type=3
Dn Slope=0.005
Boundary for River Rch & Prof#=Stream0416,Reach-1,4
Up Type=0
Dn Type=3
Dn Slope=0.005
Boundary for River Rch & Prof#=Stream0416,Reach-1,5
Up Type=0
Dn Type=3
Dn Slope=0.005
Boundary for River Rch & Prof#=Stream0416,Reach-1,6
Up Type=0
Dn Type=3
Dn Slope=0.005
Boundary for River Rch & Prof#=Stream0416,Reach-1,7
Up Type=0
Dn Type=3
Dn Slope=0.005

--- Stream0416.g01 (geometry) ---

Geom Title=Existing Conditions

River Reach=Stream0416,Reach-1
Reach XY= 30
      1872825.00     13971525.00      1872825.65     13971404.46
      1872821.99     13971383.25      1872813.33     13971376.97
      1872781.53     13971372.27      1872769.31     13971366.68
      1872691.75     13971291.46      1872673.53     13971278.55
      1872645.18     13971274.57      1872459.82     13971275.44
      1872430.93     13971272.76      1872415.33     13971264.20
      1872377.18     13971231.12      1872322.82     13971218.89
      1872273.42     13971178.83      1872254.91     13971175.23
      1872180.98     13971172.64      1872165.37     13971164.11
      1872131.06     13971133.14      1872114.50     13971126.22
      1871745.03     13971124.93      1871722.67     13971119.25
      1871681.06     13971083.14      1871664.50     13971076.22
      1871435.50     13971073.80      1871418.92     13971066.91
      1871373.27     13971029.17      1871322.75     13971019.05
      1871273.51     13970978.60      1871225.00     13970975.00

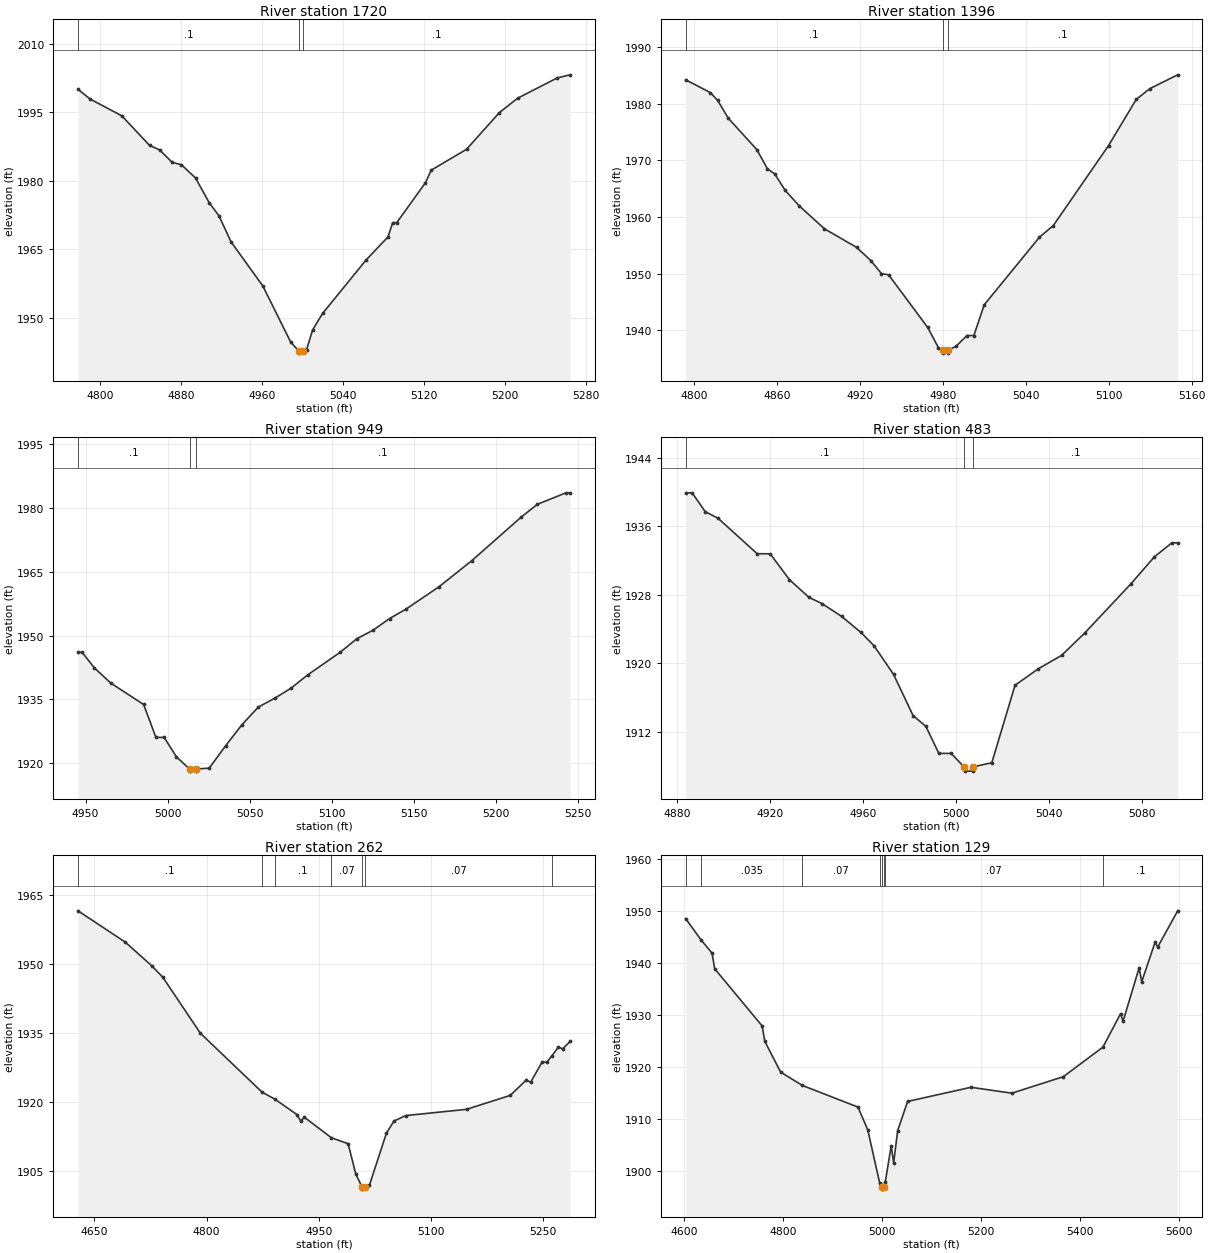
Type RM Length L Ch R = 1,1720,324,324,324
BEGIN DESCRIPTION:
Stream0416 4.0
END DESCRIPTION:
XS GIS Cut Line= 3
      1872922.89     13971184.61      1872765.43     13971456.96
      1872738.56     13971625.95
#Sta/Elev= 30
  4778.2 2000.09  4790.2 1997.94  4821.5 1994.26  4848.8 1987.79  4858.8 1986.79
  4871.1 1984.07  4880.3 1983.54  4894.2 1980.64  4907.7 1975.22  4917.3 1972.36
  4929.2 1966.66  4960.7 1956.94  4988.1 1944.67  4996.0 1942.74  4996.3 1942.24
  5000.0 1942.74  5003.8 1942.98  5009.7 1947.29  5019.6 1950.94  5062.7 1962.70
  5084.2 1967.73  5088.8 1970.84  5092.8 1970.84  5121.2 1979.62  5126.8 1982.35
  5161.7 1986.93  5194.1 1994.98  5212.3 1998.15  5251.2 2002.58  5263.9 2003.26
#Mann=3,-1,0
  4778.2     0.1       0  4996.0    0.05       0  5000.0     0.1       0
Bank Sta=4996,5000
Exp/Cntr=0.3,0.1

Type RM Length L Ch R = 1,1396,447,447,447
BEGIN DESCRIPTION:
Stream0416 3.0
END DESCRIPTION:
XS GIS Cut Line= 3
      1872574.99     13971075.03      1872525.00     13971275.00
      1872525.00     13971424.97
#Sta/Elev= 30
  4793.8 1984.27  4811.8 1981.98  4817.0 1980.60  4824.7 1977.46  4845.3 1971.92
  4853.0 1968.52  4858.2 1967.64  4865.9 1964.69  4876.2 1961.92  4894.3 1957.90
  4917.5 1954.63  4927.8 1952.30  4935.5 1949.99  4940.7 1949.77  4969.0 1940.46
  4976.7 1936.90  4979.9 1936.42  4980.1 1935.92  4983.6 1935.92  4983.9 1936.42
  4989.6 1937.16  4997.4 1939.03  5002.4 1939.03  5009.9 1944.47  5049.9 1956.43
  5059.9 1958.48  5099.9 1972.64  5119.9 1980.79  5129.9 1982.72  5149.9 1985.14
#Mann=3,-1,0
  4793.8     0.1       0  4979.9    0.05       0  4983.9     0.1       0
Bank Sta=4979.9,4983.9
Exp/Cntr=0.3,0.1

Type RM Length L Ch R = 1,949,466,466,466
BEGIN DESCRIPTION:
Stream0416 2.0
END DESCRIPTION:
XS GIS Cut Line= 3
      1872125.00     13971074.97      1872125.00     13971125.00
      1872125.00     13971374.97
#Sta/Elev= 30
  4945.4 1946.06  4947.9 1946.06  4955.4 1942.38  4965.4 1938.81  4985.4 1933.78
  4992.9 1926.03  4997.9 1926.03  5005.4 1921.47  5013.4 1918.60  5013.7 1918.10
  5017.2 1918.10  5017.4 1918.60  5025.4 1918.80  5035.4 1924.07  5045.4 1929.05
  5055.4 1933.19  5065.4 1935.26  5075.4 1937.66  5085.4 1940.73  5105.4 1946.11
  5115.4 1949.26  5125.4 1951.28  5135.4 1954.01  5145.4 1956.23  5165.4 1961.45
  5185.4 1967.59  5215.4 1977.80  5225.4 1980.87  5242.9 1983.58  5245.4 1983.58
#Mann=3,-1,0
  4945.4     0.1       0  5013.4    0.05       0  5017.4     0.1       0
Bank Sta=5013.4,5017.4
Exp/Cntr=0.3,0.1

Type RM Length L Ch R = 1,483,221,221,221
BEGIN DESCRIPTION:
Stream0416 1.0
END DESCRIPTION:
XS GIS Cut Line= 3
      1871725.01     13970974.98      1871675.00     13971075.00
      1871675.00     13971174.97
#Sta/Elev= 30
  4883.6 1939.93  4886.4 1939.93  4892.0 1937.74  4897.6 1936.95  4914.4 1932.82
  4920.0 1932.81  4928.3 1929.78  4936.7 1927.72  4942.3 1927.00  4950.7 1925.51
  4959.1 1923.62  4964.7 1922.07  4973.1 1918.73  4981.5 1913.92  4987.0 1912.66
  4992.6 1909.50  4997.9 1909.50  5003.4 1907.93  5003.7 1907.43  5007.2 1907.43
  5007.4 1907.93  5015.4 1908.41  5025.4 1917.46  5035.4 1919.38  5045.4 1920.94
  5055.4 1923.56  5075.4 1929.34  5085.4 1932.46  5092.9 1934.09  5095.4 1934.09
#Mann=3,-1,0
  4883.6     0.1       0  5003.4    0.05       0  5007.4     0.1       0
Bank Sta=5003.4,5007.4
Exp/Cntr=0.3,0.1

Type RM Length L Ch R = 1,262,133,133,133
BEGIN DESCRIPTION:
Stream0416 0.0
END DESCRIPTION:
XS GIS Cut Line= 4
      1871608.91     13970761.12      1871437.79     13970996.09
      1871481.87     13971194.00      1871623.64     13971277.95
#Sta/Elev= 30
  4628.1 1961.48  4691.4 1954.67  4726.9 1949.52  4741.6 1947.03  4791.8 1934.89
  4874.4 1922.08  4891.2 1920.60  4920.8 1917.24  4925.9 1915.84  4931.0 1916.63
  4967.1 1912.18  4989.4 1910.90  4999.6 1904.34  5007.9 1901.53  5008.1 1901.03
  5011.9 1901.53  5018.0 1901.93  5040.6 1913.17  5050.8 1915.83  5066.6 1917.01
  5147.8 1918.36  5206.3 1921.39  5227.7 1924.72  5233.5 1924.25  5249.1 1928.69
  5254.9 1928.57  5262.3 1930.05  5270.6 1931.88  5276.4 1931.50  5286.3 1933.10
#Mann=7,-1,0
  4628.1     0.1       0  4874.4    0.07       0  4891.2     0.1       0
  4967.1    0.07       0  5007.9    0.05       0  5011.9    0.07       0
  5262.3     0.1       0
Bank Sta=5007.9,5011.9
Exp/Cntr=0.3,0.1

Type RM Length L Ch R = 1,129,0,0,0
BEGIN DESCRIPTION:
Stream0416 0.1
END DESCRIPTION:
XS GIS Cut Line= 5
      1871438.06     13970644.16      1871332.17     13970970.52
      1871346.06     13971100.73      1871417.24     13971272.60
      1871734.97     13971373.30
#Sta/Elev= 30
  4603.4 1948.46  4634.6 1944.34  4656.8 1941.81  4662.0 1938.81  4757.9 1927.80
  4763.2 1924.86  4795.2 1918.93  4839.2 1916.36  4951.3 1912.21  4971.1 1907.83
  4995.4 1897.52  4999.3 1896.93  4999.6 1896.43  5003.3 1896.93  5006.5 1897.80
  5018.4 1904.75  5023.4 1901.51  5031.5 1907.68  5051.6 1913.29  5179.5 1916.01
  5262.1 1914.88  5366.0 1918.05  5445.9 1923.73  5481.4 1930.15  5486.6 1928.70
  5518.9 1938.95  5524.2 1936.30  5551.2 1943.90  5556.4 1942.97  5596.8 1949.94
#Mann=8,-1,0
  4603.4    0.07       0  4634.6   0.035       0  4839.2    0.07       0
  4995.4     0.1       0  4999.3    0.05       0  5003.3     0.1       0
  5006.5    0.07       0  5445.9     0.1       0
Bank Sta=4999.3,5003.3
Exp/Cntr=0.3,0.1

Chan Stop Cuts=-1