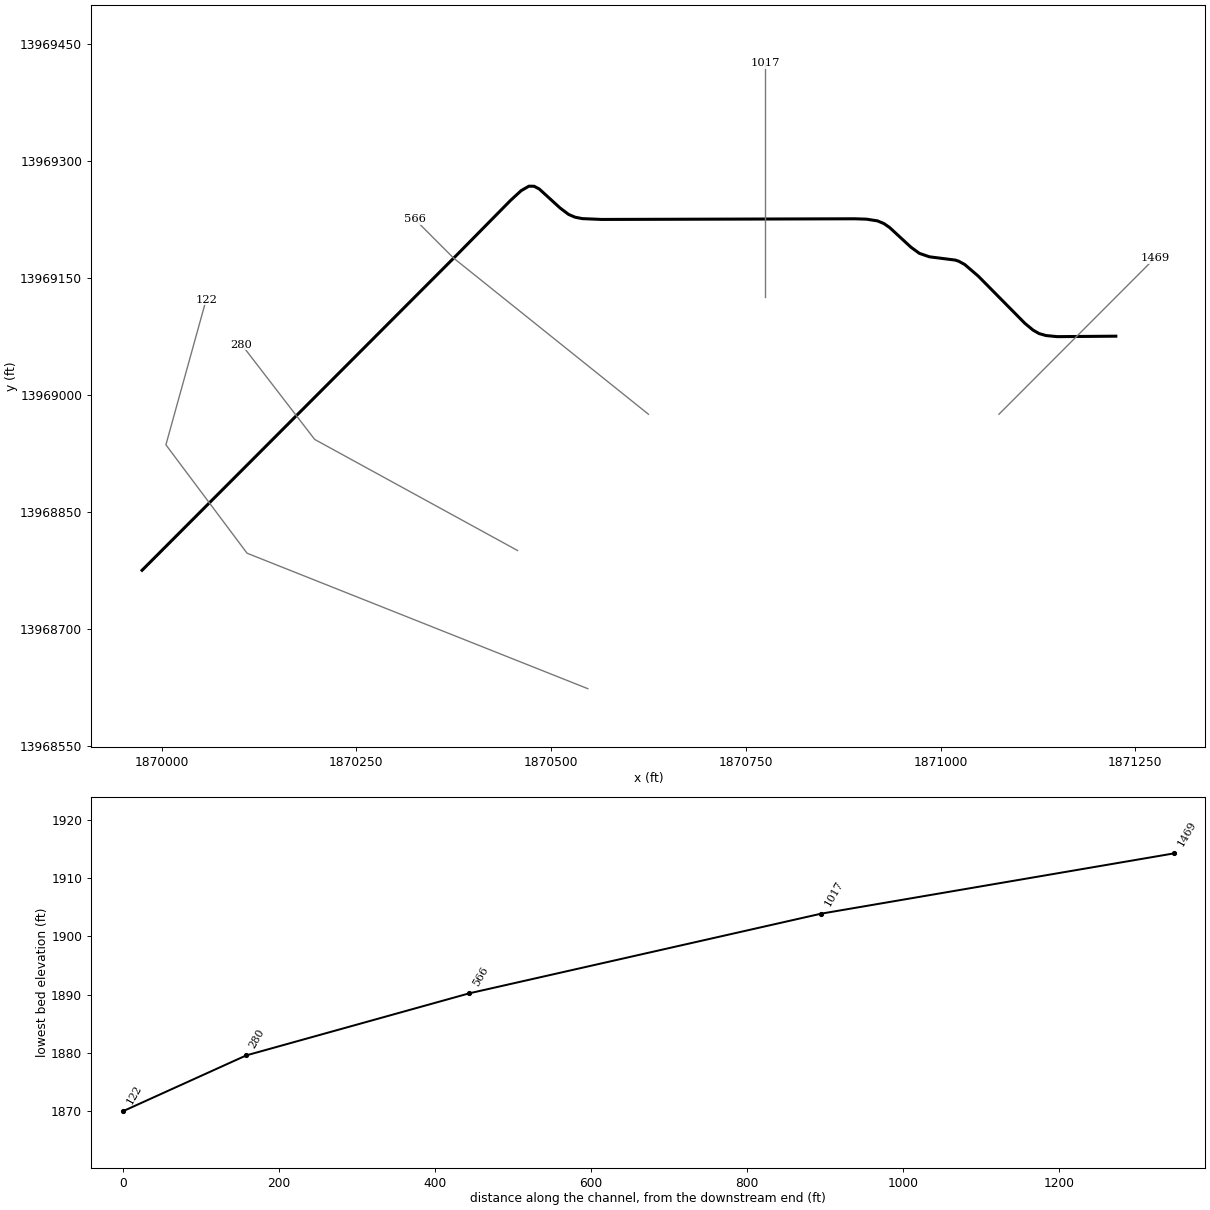
--- Stream0418.prj (project) ---

Proj Title=Stream0418 Base Level Engineering
Current Plan=p01
Default Exp/Contr=0.3,0.1
English Units
Geom File=g01
Flow File=f01
Plan File=p01
BEGIN DESCRIPTION:
Stream0418
END DESCRIPTION:

--- Stream0418.p01 (plan) ---

Plan Title=Multiple Run
Short Identifier=Multiple
Geom File=g01
Flow File=f01
Subcritical Flow
K Sum by GR= 0
Std Step Tol= 0.01
Critical Tol= 0.01
Num of Std Step Trials= 20
Max Error Tol= 0.3
Flow Tol Ratio= 0.001
Split Flow NTrial= 30
Split Flow Tol= 0.02
Split Flow Ratio= 0.02
Log Output Level= 0
Friction Slope Method= 1
Unsteady Friction Slope Method= 2
Unsteady Bridges Friction Slope Method= 1
Parabolic Critical Depth
Global Vel Dist=  1 , 1 , 1
Global Log Level= 0
CheckData=True
Encroach Param= -1, 0, 0, 0
BEGIN DESCRIPTION:
Multiple Run
END DESCRIPTION:

--- Stream0418.f01 (steady flow) ---

Flow Title=Multiple
Number of Profiles=7
Profile Names=10-year,25-year,50-year,1pct_min,100-year,1pct_plu,500-year
River Rch & RM= Stream0418,Reach-1,1469
     454     732     983     641    1279    2553    2132
Boundary for River Rch & Prof#=Stream0418,Reach-1,1
Up Type=0
Dn Type=3
Dn Slope=0.005
Boundary for River Rch & Prof#=Stream0418,Reach-1,2
Up Type=0
Dn Type=3
Dn Slope=0.005
Boundary for River Rch & Prof#=Stream0418,Reach-1,3
Up Type=0
Dn Type=3
Dn Slope=0.005
Boundary for River Rch & Prof#=Stream0418,Reach-1,4
Up Type=0
Dn Type=3
Dn Slope=0.005
Boundary for River Rch & Prof#=Stream0418,Reach-1,5
Up Type=0
Dn Type=3
Dn Slope=0.005
Boundary for River Rch & Prof#=Stream0418,Reach-1,6
Up Type=0
Dn Type=3
Dn Slope=0.005
Boundary for River Rch & Prof#=Stream0418,Reach-1,7
Up Type=0
Dn Type=3
Dn Slope=0.005

--- Stream0418.g01 (geometry) ---

Geom Title=Existing Conditions

River Reach=Stream0418,Reach-1
Reach XY= 30
      1871225.00     13969075.00      1871149.76     13969074.41
      1871135.34     13969075.82      1871126.41     13969078.39
      1871118.78     13969082.76      1871108.25     13969091.47
      1871048.45     13969151.94      1871031.05     13969166.84
      1871023.36     13969171.05      1871018.96     13969172.50
      1870985.71     13969176.72      1870972.83     13969181.14
      1870961.97     13969189.05      1870934.67     13969214.21
      1870927.35     13969219.29      1870919.07     13969222.76
      1870904.97     13969224.94      1870890.18     13969225.44
      1870564.79     13969224.60      1870540.16     13969225.66
      1870530.85     13969227.47      1870522.55     13969231.03
      1870511.68     13969239.22      1870484.84     13969263.67
      1870478.21     13969267.13      1870471.58     13969267.21
      1870461.62     13969261.47      1870448.31     13969249.28
      1870378.33     13969178.36      1869975.00     13968775.00

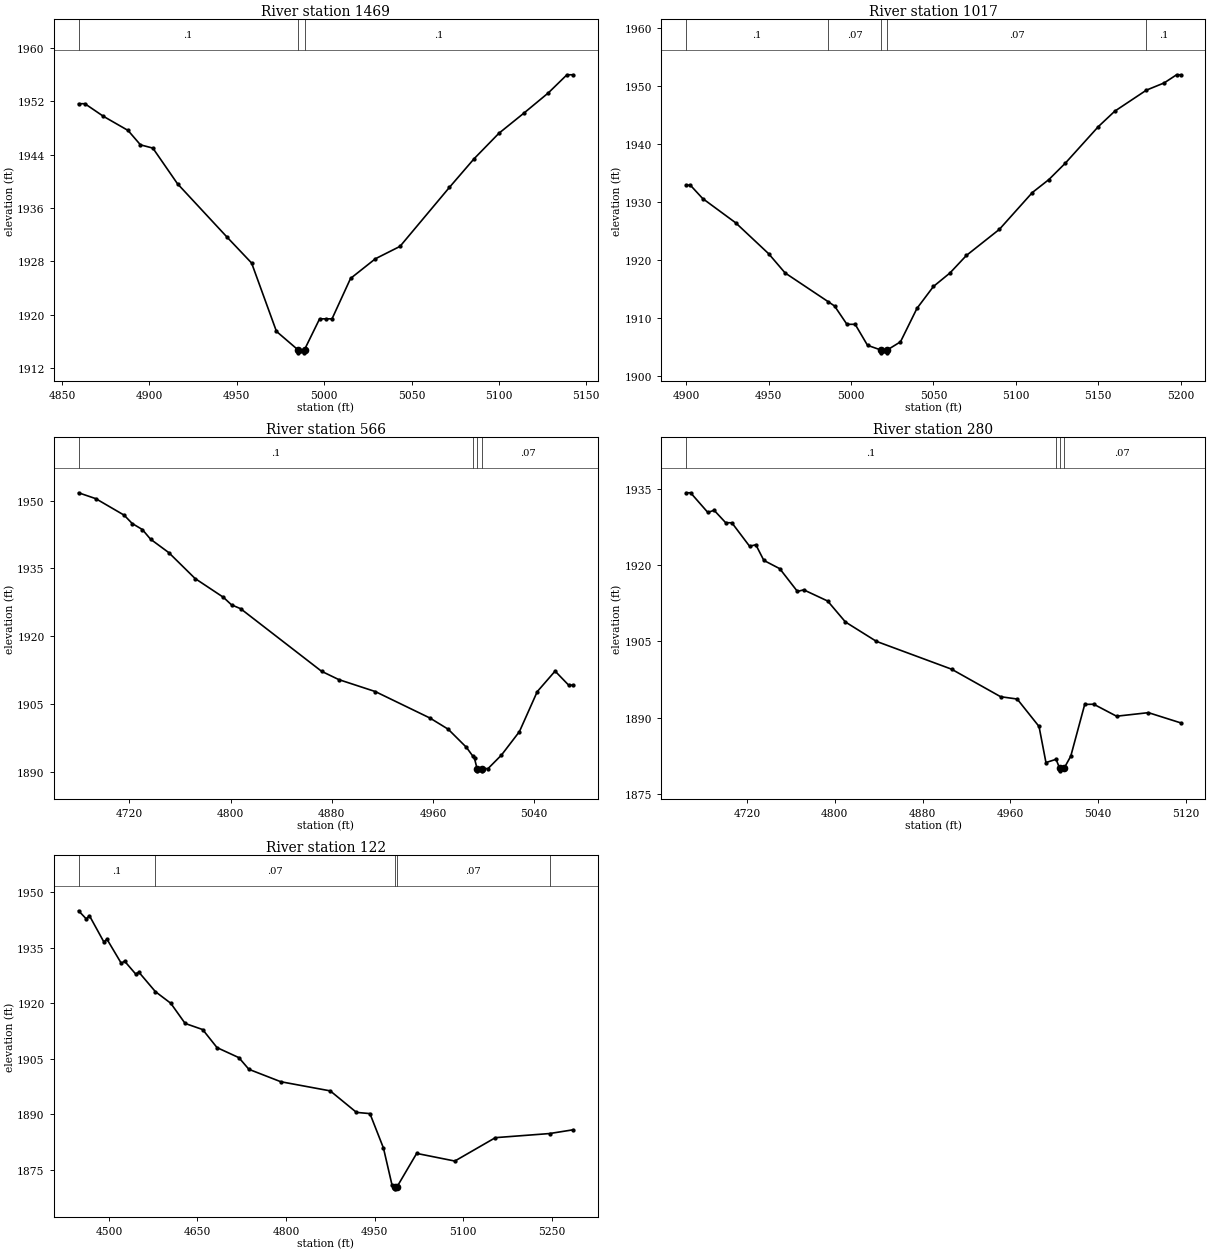
Type RM Length L Ch R = 1,1469,452,452,452
BEGIN DESCRIPTION:
Stream0418 3.0
END DESCRIPTION:
XS GIS Cut Line= 3
      1871074.97     13968974.97      1871175.00     13969075.00
      1871275.01     13969175.01
#Sta/Elev= 27
  4859.5 1951.66  4863.1 1951.66  4873.7 1949.77  4887.8 1947.65  4894.9 1945.49
  4902.0 1945.00  4916.1 1939.65  4944.4 1931.66  4958.5 1927.76  4972.7 1917.51
  4984.8 1914.79  4985.1 1914.29  4988.6 1914.29  4988.8 1914.79  4997.4 1919.39
  5001.0 1919.39  5004.5 1919.39  5015.1 1925.45  5029.3 1928.40  5043.4 1930.26
  5071.7 1939.12  5085.8 1943.41  5100.0 1947.23  5114.1 1950.21  5128.2 1953.27
  5138.9 1956.00  5142.4 1956.00
#Mann=3,-1,0
  4859.5     0.1       0  4984.8    0.05       0  4988.8     0.1       0
Bank Sta=4984.8,4988.8
Exp/Cntr=0.3,0.1

Type RM Length L Ch R = 1,1017,451,451,451
BEGIN DESCRIPTION:
Stream0418 2.0
END DESCRIPTION:
XS GIS Cut Line= 3
      1870775.00     13969125.04      1870775.00     13969225.00
      1870775.00     13969425.04
#Sta/Elev= 30
  4900.0 1932.84  4902.5 1932.84  4910.0 1930.53  4930.0 1926.35  4950.0 1921.02
  4960.0 1917.70  4986.2 1912.73  4990.0 1912.00  4997.5 1908.84  5002.5 1908.84
  5010.0 1905.22  5018.0 1904.42  5018.2 1903.92  5021.7 1903.92  5022.0 1904.42
  5030.0 1905.82  5040.0 1911.59  5050.0 1915.37  5060.0 1917.69  5070.0 1920.72
  5090.0 1925.22  5110.0 1931.57  5120.0 1933.80  5130.0 1936.63  5150.0 1942.93
  5160.0 1945.60  5179.2 1949.23  5190.0 1950.48  5197.5 1951.88  5200.0 1951.88
#Mann=5,-1,0
  4900.0     0.1       0  4986.2    0.07       0  5018.0    0.05       0
  5022.0    0.07       0  5179.2     0.1       0
Bank Sta=5018,5022
Exp/Cntr=0.3,0.1

Type RM Length L Ch R = 1,566,286,286,286
BEGIN DESCRIPTION:
Stream0418 1.0
END DESCRIPTION:
XS GIS Cut Line= 3
      1870625.02     13968974.99      1870375.00     13969175.00
      1870324.99     13969225.01
#Sta/Elev= 30
  4679.8 1951.74  4693.4 1950.44  4715.8 1946.79  4722.2 1944.94  4730.2 1943.61
  4736.7 1941.47  4751.1 1938.50  4771.9 1932.77  4794.3 1928.61  4800.7 1926.94
  4807.9 1926.09  4871.9 1912.24  4885.5 1910.40  4914.3 1907.76  4957.6 1901.89
  4972.0 1899.42  4986.4 1895.41  4991.4 1893.49  4992.8 1892.95  4994.8 1890.71
  4995.0 1890.21  4998.5 1890.21  4998.8 1890.71  5003.5 1890.71  5014.1 1893.70
  5028.3 1898.89  5042.4 1907.74  5056.5 1912.28  5067.2 1909.18  5070.7 1909.18
#Mann=4,-1,0
  4679.8     0.1       0  4991.4    0.07       0  4994.8    0.05       0
  4998.8    0.07       0
Bank Sta=4994.8,4998.8
Exp/Cntr=0.3,0.1

Type RM Length L Ch R = 1,280,158,158,158
BEGIN DESCRIPTION:
Stream0418 0.0
END DESCRIPTION:
XS GIS Cut Line= 3
      1870457.00     13968800.36      1870196.59     13968942.71
      1870102.82     13969064.27
#Sta/Elev= 30
  4664.8 1934.24  4668.8 1934.24  4684.5 1930.37  4690.2 1930.80  4700.7 1928.36
  4706.4 1928.33  4722.5 1923.72  4728.2 1924.01  4735.5 1920.93  4750.0 1919.30
  4766.1 1914.82  4771.8 1915.14  4793.6 1912.94  4809.8 1908.81  4838.0 1905.00
  4906.4 1899.53  4951.1 1894.11  4966.2 1893.65  4986.1 1888.25  4992.4 1881.15
  5001.6 1881.79  5004.9 1880.02  5005.1 1879.52  5008.9 1880.02  5015.0 1882.41
  5027.7 1892.59  5035.9 1892.63  5056.7 1890.27  5085.7 1890.97  5115.1 1888.96
#Mann=4,-1,0
  4664.8     0.1       0  5001.6    0.07       0  5004.9    0.05       0
  5008.9    0.07       0
Bank Sta=5004.9,5008.9
Exp/Cntr=0.3,0.1

Type RM Length L Ch R = 1,122,0,0,0
BEGIN DESCRIPTION:
Stream0418 4.0
END DESCRIPTION:
XS GIS Cut Line= 4
      1870547.25     13968623.28      1870109.79     13968796.88
      1870005.62     13968935.77      1870057.26     13969121.67
#Sta/Elev= 30
  4448.7 1944.94  4461.7 1942.75  4467.1 1943.61  4491.4 1936.56  4496.8 1937.26
  4521.1 1930.74  4526.5 1931.37  4545.4 1927.87  4550.8 1928.37  4578.7 1923.13
  4604.8 1919.98  4629.1 1914.54  4658.8 1912.89  4683.1 1908.02  4720.1 1905.31
  4737.1 1902.16  4791.1 1898.81  4874.8 1896.34  4919.2 1890.54  4942.0 1890.21
  4964.9 1880.91  4979.5 1870.87  4983.7 1870.41  4984.0 1869.91  4987.7 1870.41
  5021.1 1879.47  5085.7 1877.41  5154.4 1883.72  5246.2 1884.83  5285.9 1885.84
#Mann=5,-1,0
  4448.7     0.1       0  4578.7    0.07       0  4983.7    0.05       0
  4987.7    0.07       0  5246.2     0.1       0
Bank Sta=4983.7,4987.7
Exp/Cntr=0.3,0.1

Chan Stop Cuts=-1