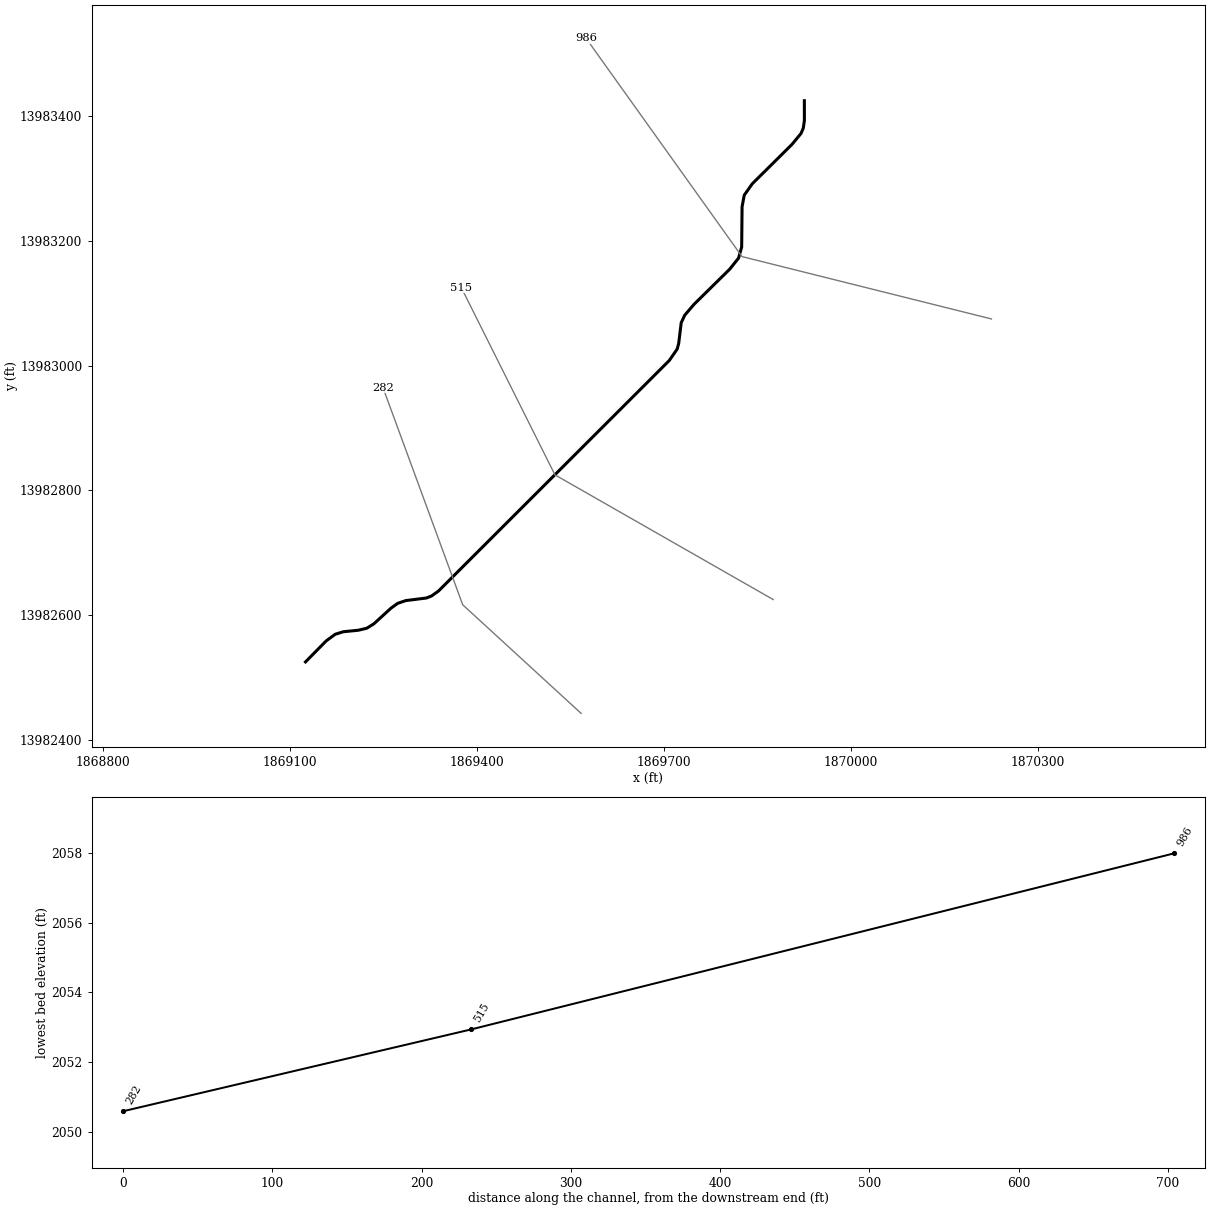
--- Stream0420.prj (project) ---

Proj Title=Stream0420 Base Level Engineering
Current Plan=p01
Default Exp/Contr=0.3,0.1
English Units
Geom File=g01
Flow File=f01
Plan File=p01
Y Axis Title=Elevation
X Axis Title(PF)=Main Channel Distance
X Axis Title(XS)=Station
BEGIN DESCRIPTION:
Stream0420
END DESCRIPTION:
DSS Export Rating Curves= 0
DSS Export Rating Curve Sorted= 0
DSS Export Volume Flow Curves= 0
DXF OffsetX= 0
DXF OffsetY= 0
DXF ScaleX= 1
DXF ScaleY= 10

--- Stream0420.p01 (plan) ---

Plan Title=Multiple Run
Short Identifier=Multiple
Geom File=g01
Flow File=f01
Subcritical Flow
K Sum by GR= 0
Std Step Tol= 0.01
Critical Tol= 0.01
Num of Std Step Trials= 20
Max Error Tol= 0.3
Flow Tol Ratio= 0.001
Split Flow NTrial= 30
Split Flow Tol= 0.02
Split Flow Ratio= 0.02
Log Output Level= 0
Friction Slope Method= 1
Unsteady Friction Slope Method= 2
Unsteady Bridges Friction Slope Method= 1
Parabolic Critical Depth
Global Vel Dist=  1 , 1 , 1
Global Log Level= 0
CheckData=True
Encroach Param= -1, 0, 0, 0
BEGIN DESCRIPTION:
Multiple Run
END DESCRIPTION:

--- Stream0420.f01 (steady flow) ---

Flow Title=Multiple
Program Version=4.10
Number of Profiles= 7
Profile Names=10-year,25-year,50-year,1pct_min,100-year,1pct_plu,500-year
River Rch & RM=Stream0420,Reach-1         ,986
    1291    2212    3092    2087    4164    8308    7461
Boundary for River Rch & Prof#=Stream0420,Reach-1         , 1
Up Type= 0
Dn Type= 3
Dn Slope=0.01
Boundary for River Rch & Prof#=Stream0420,Reach-1         , 2
Up Type= 0
Dn Type= 3
Dn Slope=0.01
Boundary for River Rch & Prof#=Stream0420,Reach-1         , 3
Up Type= 0
Dn Type= 3
Dn Slope=0.01
Boundary for River Rch & Prof#=Stream0420,Reach-1         , 4
Up Type= 0
Dn Type= 3
Dn Slope=0.01
Boundary for River Rch & Prof#=Stream0420,Reach-1         , 5
Up Type= 0
Dn Type= 3
Dn Slope=0.01
Boundary for River Rch & Prof#=Stream0420,Reach-1         , 6
Up Type= 0
Dn Type= 3
Dn Slope=0.01
Boundary for River Rch & Prof#=Stream0420,Reach-1         , 7
Up Type= 0
Dn Type= 3
Dn Slope=0.01
DSS Import GetInterval= 0
DSS Import GetPeak= 0
DSS Import FillOption= 0

--- Stream0420.g01 (geometry) ---

Geom Title=Existing Conditions

River Reach=Stream0420,Reach-1
Reach XY= 30
      1869925.00     13983425.00      1869925.07     13983393.12
      1869923.31     13983381.15      1869919.67     13983372.49
      1869905.17     13983354.93      1869841.46     13983291.75
      1869828.61     13983273.50      1869825.13     13983254.94
      1869824.47     13983190.22      1869819.46     13983172.58
      1869805.33     13983154.86      1869748.07     13983098.44
      1869733.18     13983081.04      1869727.54     13983068.95
      1869723.45     13983035.64      1869721.03     13983026.65
      1869708.35     13983008.33      1869338.22     13982638.62
      1869327.30     13982630.83      1869318.97     13982627.50
      1869285.70     13982623.30      1869272.81     13982618.90
      1869261.93     13982611.03      1869234.57     13982586.04
      1869223.33     13982579.04      1869209.68     13982575.77
      1869185.66     13982573.40      1869172.64     13982569.33
      1869158.07     13982558.59      1869125.00     13982525.00

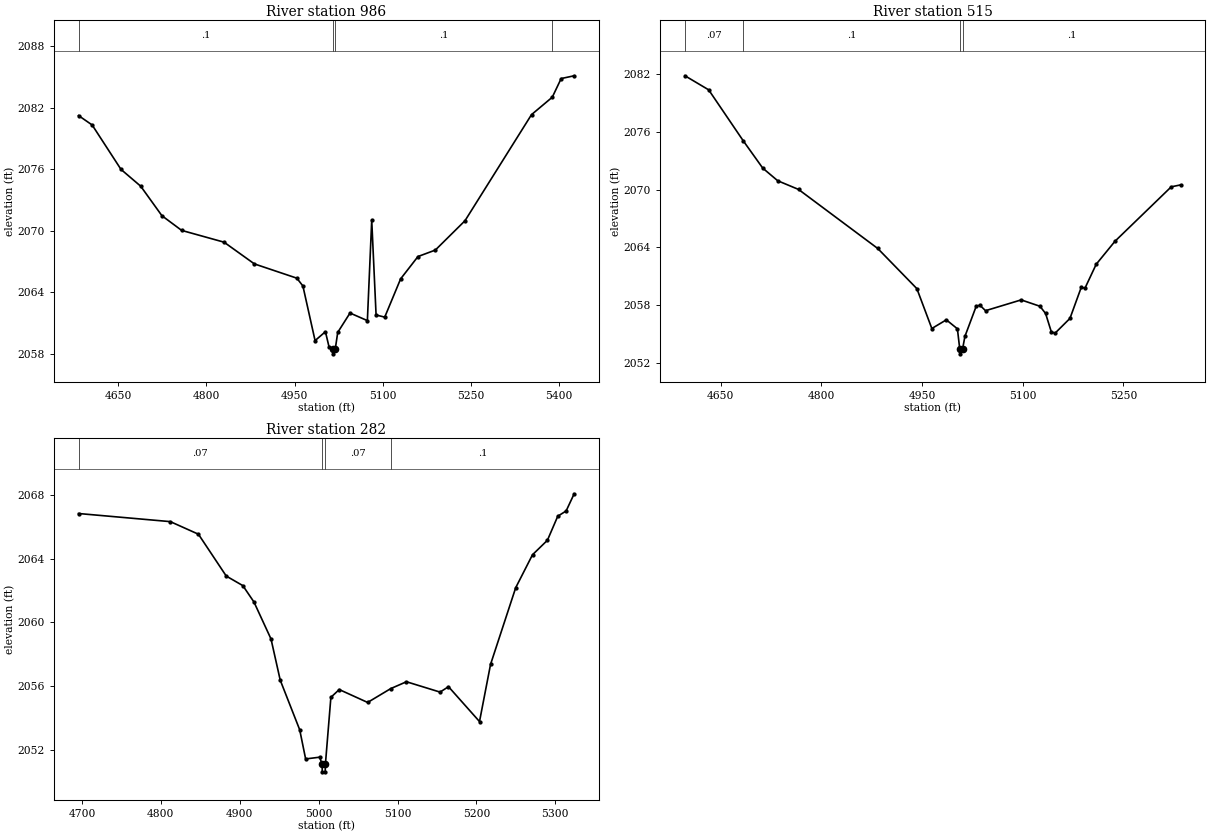
Type RM Length L Ch R = 1,986,471,471,471
BEGIN DESCRIPTION:
Stream0420 2.0
END DESCRIPTION:
XS GIS Cut Line= 3
      1870225.05     13983074.99      1869825.00     13983175.00
      1869574.99     13983525.02
#Sta/Elev= 30
  4582.8 2081.22  4606.0 2080.30  4655.0 2075.97  4688.5 2074.33  4724.6 2071.45
  4758.1 2070.02  4830.2 2068.87  4881.8 2066.75  4953.9 2065.36  4964.2 2064.60
  4984.9 2059.27  5002.5 2060.14  5008.7 2058.64  5015.2 2058.48  5015.5 2057.98
  5019.3 2058.48  5023.4 2060.07  5044.3 2061.96  5073.8 2061.22  5081.2 2071.01
  5088.6 2061.77  5103.3 2061.56  5130.3 2065.29  5159.8 2067.47  5189.3 2068.10
  5239.7 2070.96  5352.8 2081.31  5388.1 2083.01  5403.2 2084.83  5425.3 2085.10
#Mann=4,-1,0
  4582.8     0.1       0  5015.2    0.05       0  5019.3     0.1       0
  5388.1   0.035       0
Bank Sta=5015.2,5019.3
Exp/Cntr=0.3,0.1

Type RM Length L Ch R = 1,515,233,233,233
BEGIN DESCRIPTION:
Stream0420 1.0
END DESCRIPTION:
XS GIS Cut Line= 3
      1869875.00     13982625.00      1869525.00     13982825.00
      1869375.01     13983124.98
#Sta/Elev= 30
  4596.9 2081.81  4632.2 2080.35  4683.5 2075.08  4712.8 2072.22  4735.1 2070.91
  4766.1 2070.01  4884.1 2063.88  4942.4 2059.71  4964.7 2055.57  4986.3 2056.47
  5002.8 2055.54  5006.3 2053.44  5006.5 2052.94  5010.5 2053.44  5014.0 2054.75
  5030.8 2057.88  5036.3 2057.99  5044.7 2057.42  5097.8 2058.54  5125.8 2057.88
  5134.2 2057.13  5142.6 2055.25  5148.1 2055.07  5170.5 2056.62  5187.3 2059.84
  5192.9 2059.76  5209.6 2062.24  5237.6 2064.63  5321.4 2070.28  5335.4 2070.48
#Mann=4,-1,0
  4596.9    0.07       0  4683.5     0.1       0  5006.3    0.05       0
  5010.5     0.1       0
Bank Sta=5006.3,5010.5
Exp/Cntr=0.3,0.1

Type RM Length L Ch R = 1,282,0,0,0
BEGIN DESCRIPTION:
Stream0420 0.0
END DESCRIPTION:
XS GIS Cut Line= 3
      1869567.00     13982442.46      1869377.06     13982616.68
      1869249.35     13982964.54
#Sta/Elev= 30
  4695.6 2066.83  4812.0 2066.32  4847.6 2065.53  4882.9 2062.90  4903.9 2062.30
  4918.0 2061.27  4939.6 2058.95  4951.3 2056.36  4976.0 2053.24  4983.5 2051.41
  5001.2 2051.52  5004.4 2051.10  5004.6 2050.60  5008.3 2050.60  5008.6 2051.10
  5015.5 2055.28  5026.1 2055.77  5062.1 2054.96  5091.4 2055.83  5111.3 2056.26
  5153.9 2055.61  5164.6 2055.95  5203.9 2053.76  5217.9 2057.35  5249.8 2062.17
  5271.1 2064.24  5290.0 2065.15  5303.1 2066.66  5313.7 2066.99  5323.9 2068.07
#Mann=4,-1,0
  4695.6    0.07       0  5004.4    0.05       0  5008.6    0.07       0
  5091.4     0.1       0
Bank Sta=5004.4,5008.6
Exp/Cntr=0.3,0.1

Chan Stop Cuts=-1