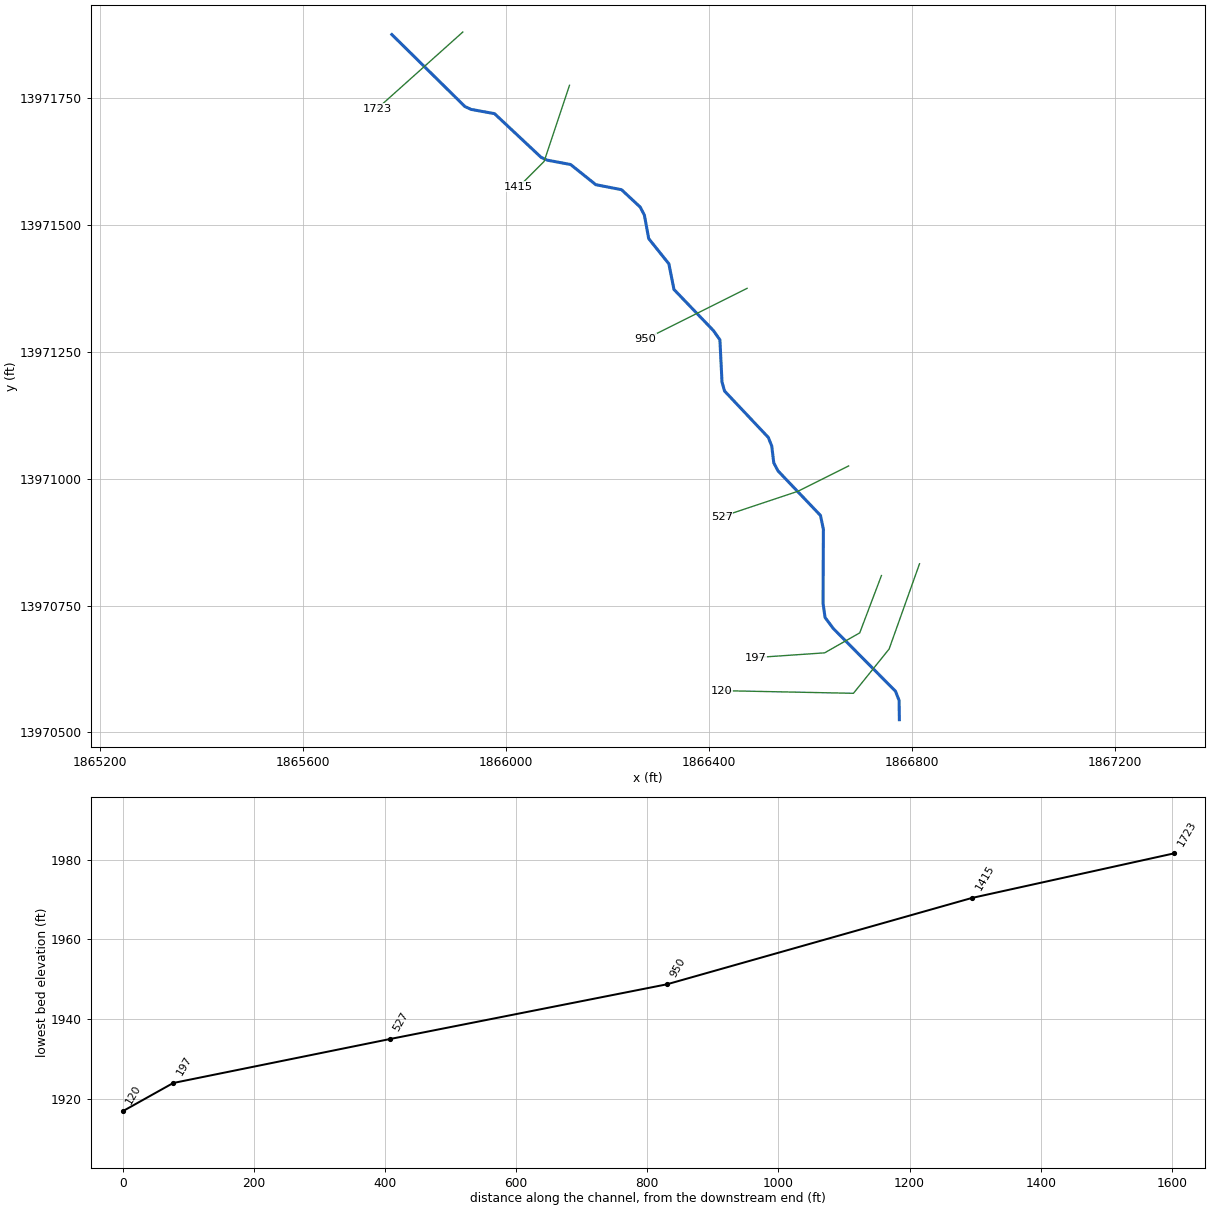
--- Stream0421.prj (project) ---

Proj Title=Stream0421 Base Level Engineering
Current Plan=p01
Default Exp/Contr=0.3,0.1
English Units
Geom File=g01
Flow File=f01
Plan File=p01
BEGIN DESCRIPTION:
Stream0421
END DESCRIPTION:

--- Stream0421.p01 (plan) ---

Plan Title=Multiple Run
Short Identifier=Multiple
Geom File=g01
Flow File=f01
Subcritical Flow
K Sum by GR= 0
Std Step Tol= 0.01
Critical Tol= 0.01
Num of Std Step Trials= 20
Max Error Tol= 0.3
Flow Tol Ratio= 0.001
Split Flow NTrial= 30
Split Flow Tol= 0.02
Split Flow Ratio= 0.02
Log Output Level= 0
Friction Slope Method= 1
Unsteady Friction Slope Method= 2
Unsteady Bridges Friction Slope Method= 1
Parabolic Critical Depth
Global Vel Dist=  1 , 1 , 1
Global Log Level= 0
CheckData=True
Encroach Param= -1, 0, 0, 0
BEGIN DESCRIPTION:
Multiple Run
END DESCRIPTION:

--- Stream0421.f01 (steady flow) ---

Flow Title=Multiple
Number of Profiles=7
Profile Names=10-year,25-year,50-year,1pct_min,100-year,1pct_plu,500-year
River Rch & RM= Stream0421,Reach-1,1723
     312     489     645     414     826    1647    1329
Boundary for River Rch & Prof#=Stream0421,Reach-1,1
Up Type=0
Dn Type=3
Dn Slope=0.005
Boundary for River Rch & Prof#=Stream0421,Reach-1,2
Up Type=0
Dn Type=3
Dn Slope=0.005
Boundary for River Rch & Prof#=Stream0421,Reach-1,3
Up Type=0
Dn Type=3
Dn Slope=0.005
Boundary for River Rch & Prof#=Stream0421,Reach-1,4
Up Type=0
Dn Type=3
Dn Slope=0.005
Boundary for River Rch & Prof#=Stream0421,Reach-1,5
Up Type=0
Dn Type=3
Dn Slope=0.005
Boundary for River Rch & Prof#=Stream0421,Reach-1,6
Up Type=0
Dn Type=3
Dn Slope=0.005
Boundary for River Rch & Prof#=Stream0421,Reach-1,7
Up Type=0
Dn Type=3
Dn Slope=0.005

--- Stream0421.g01 (geometry) ---

Geom Title=Existing Conditions

River Reach=Stream0421,Reach-1
Reach XY= 30
      1865775.00     13971875.00      1865918.95     13971733.15
      1865931.05     13971727.53      1865977.28     13971719.13
      1866068.95     13971633.16      1866081.04     13971627.51
      1866127.19     13971618.90      1866176.76     13971579.20
      1866227.55     13971569.27      1866264.37     13971535.00
      1866272.58     13971519.15      1866281.11     13971472.84
      1866320.81     13971423.27      1866330.85     13971372.71
      1866408.51     13971291.74      1866421.37     13971273.50
      1866425.53     13971190.22      1866430.54     13971172.58
      1866516.82     13971081.04      1866523.45     13971064.36
      1866527.54     13971031.05      1866535.80     13971015.33
      1866619.53     13970927.45      1866625.29     13970900.12
      1866624.57     13970754.82      1866628.54     13970726.46
      1866644.60     13970704.84      1866767.24     13970581.21
      1866774.41     13970563.16      1866775.00     13970525.00

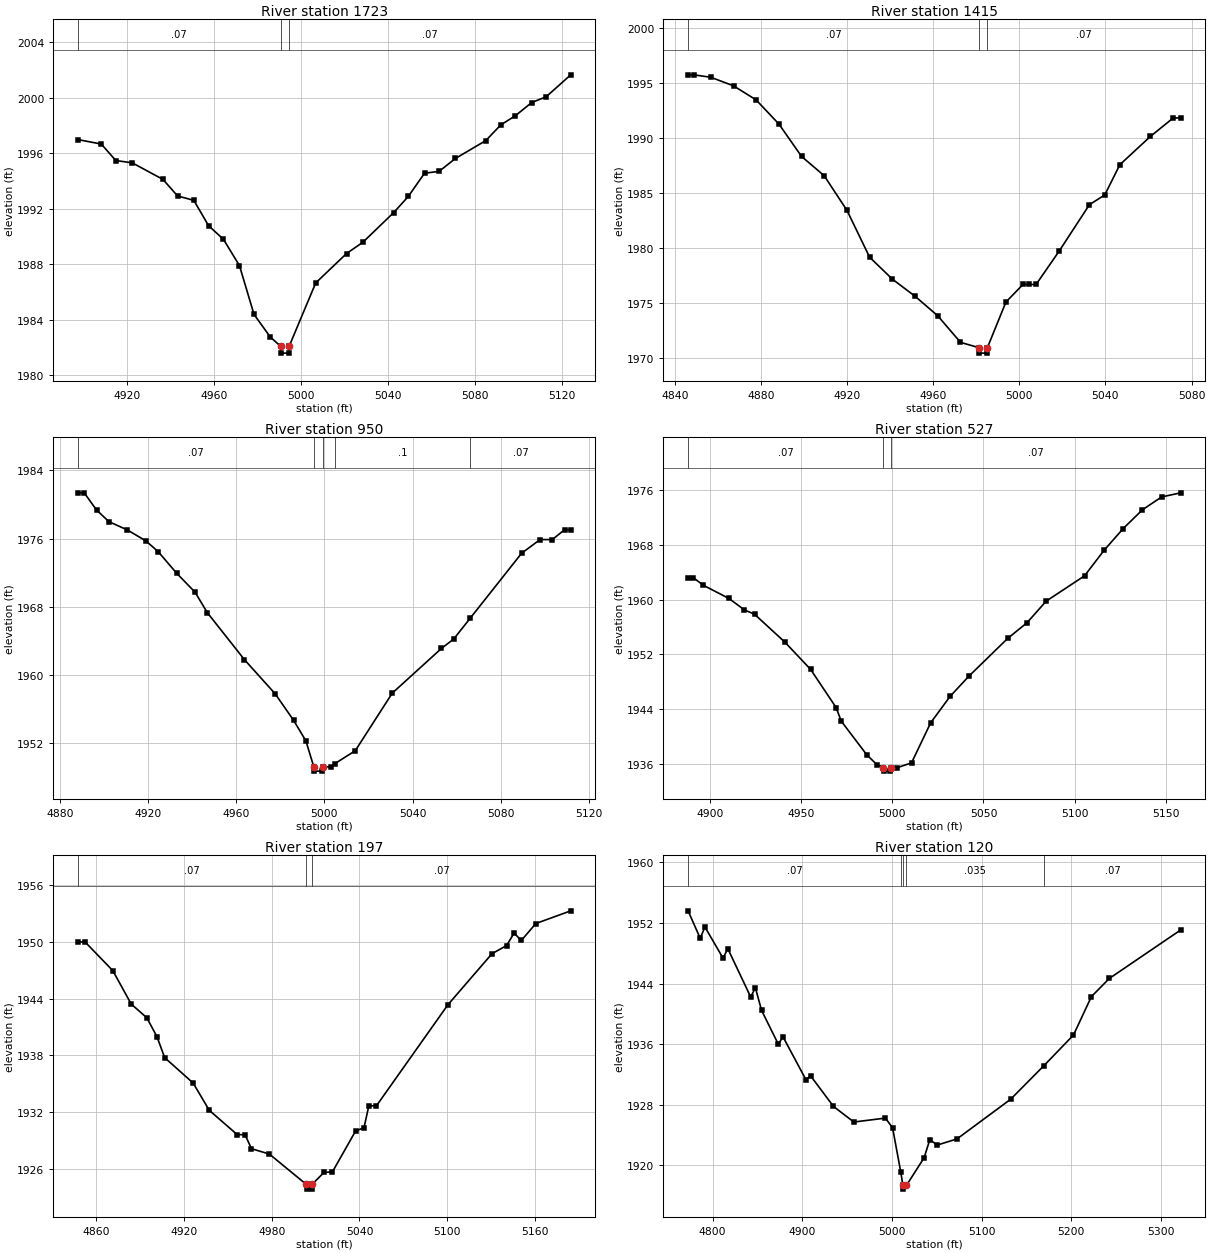
Type RM Length L Ch R = 1,1723,308,308,308
BEGIN DESCRIPTION:
Stream0421 4.0
END DESCRIPTION:
XS GIS Cut Line= 2
      1865914.84     13971879.97      1865745.85     13971728.70
#Sta/Elev= 30
  4897.4 1996.98  4908.1 1996.66  4914.8 1995.47  4922.3 1995.31  4936.5 1994.11
  4943.2 1992.92  4950.7 1992.60  4957.5 1990.77  4964.3 1989.80  4971.7 1987.90
  4978.4 1984.38  4985.9 1982.75  4990.6 1982.09  4990.8 1981.59  4994.3 1981.59
  4994.6 1982.09  5006.8 1986.65  5021.0 1988.77  5028.5 1989.58  5042.7 1991.72
  5049.4 1992.88  5056.9 1994.56  5063.6 1994.69  5071.1 1995.62  5085.1 1996.91
  5092.0 1998.04  5098.7 1998.70  5106.2 1999.65  5112.9 2000.07  5124.2 2001.65
#Mann=3,-1,0
  4897.4    0.07       0  4990.6    0.05       0  4994.6    0.07       0
Bank Sta=4990.6,4994.6
Exp/Cntr=0.3,0.1

Type RM Length L Ch R = 1,1415,465,465,465
BEGIN DESCRIPTION:
Stream0421 3.0
END DESCRIPTION:
XS GIS Cut Line= 3
      1866125.00     13971775.00      1866075.00     13971625.00
      1866025.02     13971575.02
#Sta/Elev= 29
  4846.2 1995.70  4848.8 1995.70  4856.7 1995.48  4867.3 1994.70  4877.8 1993.42
  4888.4 1991.22  4898.9 1988.28  4909.4 1986.53  4920.0 1983.37  4930.5 1979.12
  4941.1 1977.12  4951.6 1975.57  4962.1 1973.80  4972.7 1971.38  4981.2 1970.90
  4981.5 1970.40  4985.0 1970.40  4985.2 1970.90  4993.8 1975.04  5001.7 1976.64
  5004.3 1976.64  5007.8 1976.64  5018.5 1979.67  5032.6 1983.90  5039.7 1984.78
  5046.7 1987.53  5060.9 1990.10  5071.5 1991.78  5075.0 1991.78
#Mann=3,-1,0
  4846.2    0.07       0  4981.2    0.05       0  4985.2    0.07       0
Bank Sta=4981.2,4985.2
Exp/Cntr=0.3,0.1

Type RM Length L Ch R = 1,950,423,423,423
BEGIN DESCRIPTION:
Stream0421 2.0
END DESCRIPTION:
XS GIS Cut Line= 3
      1866475.02     13971375.01      1866375.00     13971325.00
      1866275.02     13971275.01
#Sta/Elev= 30
  4888.2 1981.36  4891.0 1981.36  4896.6 1979.34  4902.2 1977.98  4910.6 1977.00
  4919.0 1975.72  4924.6 1974.45  4932.9 1971.94  4941.3 1969.70  4946.9 1967.29
  4963.7 1961.79  4977.7 1957.77  4986.0 1954.68  4991.6 1952.26  4995.2 1949.21
  4995.5 1948.71  4999.0 1948.71  4999.2 1949.21  5002.8 1949.21  5004.7 1949.58
  5014.0 1951.10  5030.8 1957.86  5053.1 1963.10  5058.7 1964.21  5066.3 1966.69
  5089.5 1974.27  5097.9 1975.88  5103.4 1975.87  5109.0 1977.03  5111.8 1977.03
#Mann=5,-1,0
  4888.2    0.07       0  4995.2    0.05       0  4999.2    0.07       0
  5004.7     0.1       0  5066.3    0.07       0
Bank Sta=4995.2,4999.2
Exp/Cntr=0.3,0.1

Type RM Length L Ch R = 1,527,330,330,330
BEGIN DESCRIPTION:
Stream0421 1.0
END DESCRIPTION:
XS GIS Cut Line= 3
      1866675.03     13971025.01      1866575.00     13970975.00
      1866425.04     13970925.01
#Sta/Elev= 30
  4888.2 1963.23  4891.0 1963.23  4896.6 1962.11  4910.6 1960.18  4919.0 1958.52
  4924.6 1957.88  4941.3 1953.78  4955.3 1949.82  4969.3 1944.23  4972.1 1942.25
  4986.1 1937.32  4991.6 1935.90  4995.2 1935.44  4995.5 1934.94  4999.0 1934.94
  4999.2 1935.44  5002.7 1935.44  5010.6 1936.15  5021.1 1942.01  5031.7 1945.86
  5042.2 1948.87  5063.3 1954.35  5073.8 1956.62  5084.4 1959.80  5105.4 1963.50
  5116.0 1967.20  5126.5 1970.39  5137.1 1973.15  5147.6 1975.03  5158.1 1975.63
#Mann=3,-1,0
  4888.2    0.07       0  4995.2    0.05       0  4999.2    0.07       0
Bank Sta=4995.2,4999.2
Exp/Cntr=0.3,0.1

Type RM Length L Ch R = 1,197,77,77,77
BEGIN DESCRIPTION:
Stream0421 0.0
END DESCRIPTION:
XS GIS Cut Line= 4
      1866739.67     13970809.01      1866696.89     13970696.08
      1866627.72     13970656.71      1866491.19     13970647.35
#Sta/Elev= 30
  4847.4 1949.97  4852.2 1949.97  4871.2 1946.94  4883.8 1943.42  4894.5 1941.97
  4901.4 1939.98  4906.7 1937.77  4926.2 1935.09  4937.2 1932.22  4956.3 1929.66
  4961.7 1929.64  4966.1 1928.17  4978.3 1927.61  5003.6 1924.41  5003.9 1923.91
  5007.4 1923.91  5007.6 1924.41  5015.7 1925.67  5021.5 1925.73  5037.4 1930.05
  5043.1 1930.38  5046.4 1932.69  5051.6 1932.69  5100.6 1943.36  5130.7 1948.73
  5140.7 1949.59  5145.8 1950.90  5150.8 1950.13  5160.7 1951.91  5184.6 1953.25
#Mann=3,-1,0
  4847.4    0.07       0  5003.6    0.05       0  5007.6    0.07       0
Bank Sta=5003.6,5007.6
Exp/Cntr=0.3,0.1

Type RM Length L Ch R = 1,120,0,0,0
BEGIN DESCRIPTION:
Stream0421 0.1
END DESCRIPTION:
XS GIS Cut Line= 4
      1866814.69     13970832.23      1866754.79     13970664.23
      1866684.48     13970576.99      1866425.33     13970582.20
#Sta/Elev= 30
  4772.7 1953.61  4786.2 1949.98  4791.5 1951.47  4811.7 1947.35  4817.0 1948.61
  4842.5 1942.23  4847.8 1943.43  4854.7 1940.44  4873.3 1935.99  4878.6 1936.95
  4904.1 1931.30  4909.4 1931.79  4934.9 1927.75  4957.6 1925.69  4992.8 1926.21
  5000.8 1924.93  5010.0 1919.05  5012.3 1917.32  5012.5 1916.82  5016.3 1917.32
  5036.0 1920.97  5042.4 1923.38  5050.4 1922.64  5072.6 1923.45  5132.6 1928.71
  5169.7 1933.15  5202.6 1937.19  5222.6 1942.27  5242.6 1944.67  5322.3 1951.09
#Mann=5,-1,0
  4772.7    0.07       0  5010.0   0.035       0  5012.3    0.05       0
  5016.3   0.035       0  5169.7    0.07       0
Bank Sta=5012.3,5016.3
Exp/Cntr=0.3,0.1

Chan Stop Cuts=-1