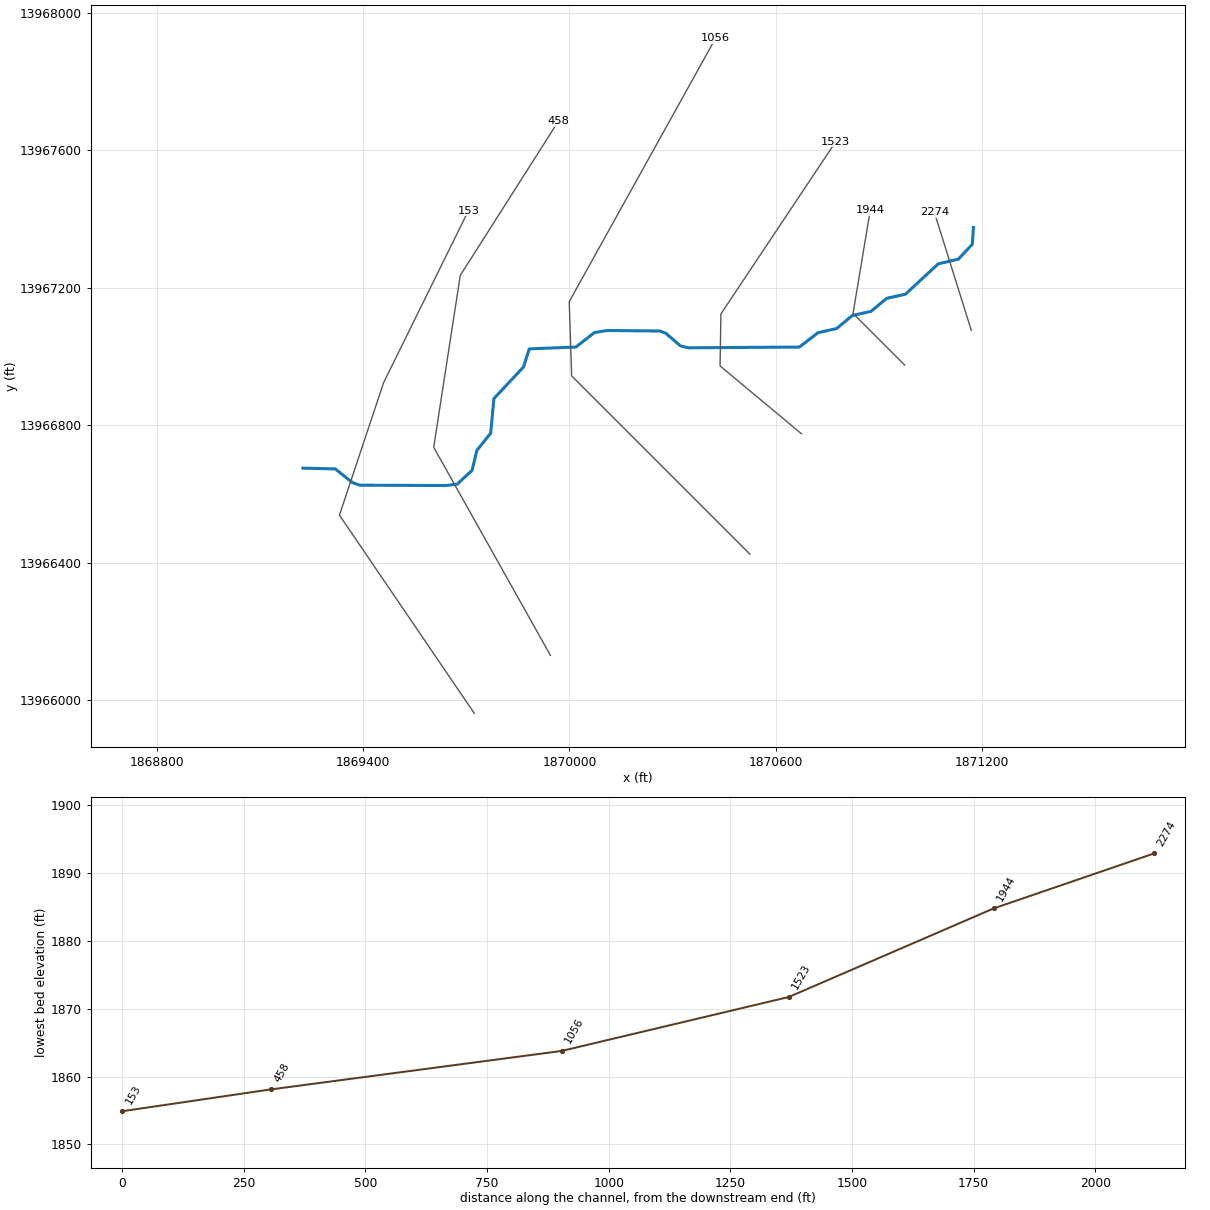
--- Stream0422.prj (project) ---

Proj Title=Stream0422 Base Level Engineering
Current Plan=p01
Default Exp/Contr=0.3,0.1
English Units
Geom File=g01
Flow File=f01
Plan File=p01
Y Axis Title=Elevation
X Axis Title(PF)=Main Channel Distance
X Axis Title(XS)=Station
BEGIN DESCRIPTION:
Stream0422
END DESCRIPTION:
DSS Export Rating Curves= 0
DSS Export Rating Curve Sorted= 0
DSS Export Volume Flow Curves= 0
DXF OffsetX= 0
DXF OffsetY= 0
DXF ScaleX= 1
DXF ScaleY= 10

--- Stream0422.p01 (plan) ---

Plan Title=Multiple Run
Short Identifier=Multiple
Geom File=g01
Flow File=f01
Subcritical Flow
K Sum by GR= 0
Std Step Tol= 0.01
Critical Tol= 0.01
Num of Std Step Trials= 20
Max Error Tol= 0.3
Flow Tol Ratio= 0.001
Split Flow NTrial= 30
Split Flow Tol= 0.02
Split Flow Ratio= 0.02
Log Output Level= 0
Friction Slope Method= 1
Unsteady Friction Slope Method= 2
Unsteady Bridges Friction Slope Method= 1
Parabolic Critical Depth
Global Vel Dist=  1 , 1 , 1
Global Log Level= 0
CheckData=True
Encroach Param= -1, 0, 0, 0
BEGIN DESCRIPTION:
Multiple Run
END DESCRIPTION:

--- Stream0422.f01 (steady flow) ---

Flow Title=Multiple
Program Version=4.10
Number of Profiles= 7
Profile Names=10-year,25-year,50-year,1pct_min,100-year,1pct_plu,500-year
River Rch & RM=Stream0422,Reach-1         ,2274
     555     909    1234     813    1621    3235    2759
Boundary for River Rch & Prof#=Stream0422,Reach-1         , 1
Up Type= 0
Dn Type= 3
Dn Slope=0.01
Boundary for River Rch & Prof#=Stream0422,Reach-1         , 2
Up Type= 0
Dn Type= 3
Dn Slope=0.01
Boundary for River Rch & Prof#=Stream0422,Reach-1         , 3
Up Type= 0
Dn Type= 3
Dn Slope=0.01
Boundary for River Rch & Prof#=Stream0422,Reach-1         , 4
Up Type= 0
Dn Type= 3
Dn Slope=0.01
Boundary for River Rch & Prof#=Stream0422,Reach-1         , 5
Up Type= 0
Dn Type= 3
Dn Slope=0.01
Boundary for River Rch & Prof#=Stream0422,Reach-1         , 6
Up Type= 0
Dn Type= 3
Dn Slope=0.01
Boundary for River Rch & Prof#=Stream0422,Reach-1         , 7
Up Type= 0
Dn Type= 3
Dn Slope=0.01
DSS Import GetInterval= 0
DSS Import GetPeak= 0
DSS Import FillOption= 0

--- Stream0422.g01 (geometry) ---

Geom Title=Existing Conditions
Program Version=4.10

River Reach=Stream0422      ,Reach-1
Reach XY= 30
        1871175.       13967375.      1871171.86     13967326.03
      1871131.31     13967282.98      1871072.73     13967269.15
      1870977.29     13967180.85      1870922.81      13967168.9
       1870877.2     13967131.08       1870822.8     13967118.92
       1870777.2     13967081.08      1870722.82     13967068.88
      1870669.07     13967027.24      1870345.03     13967025.07
      1870322.67     13967030.75      1870281.06     13967066.86
      1870264.49     13967073.78      1870109.82     13967075.43
      1870072.67     13967069.25      1870019.05     13967027.28
       1869883.3     13967021.92      1869866.68     13966969.31
      1869780.54     13966877.42      1869771.17     13966776.58
      1869731.15     13966727.15        1869717.     13966668.61
      1869673.75     13966628.45      1869640.26     13966624.49
      1869390.21     13966625.51      1869368.93      13966633.1
      1869319.13      13966672.9        1869225.       13966675.

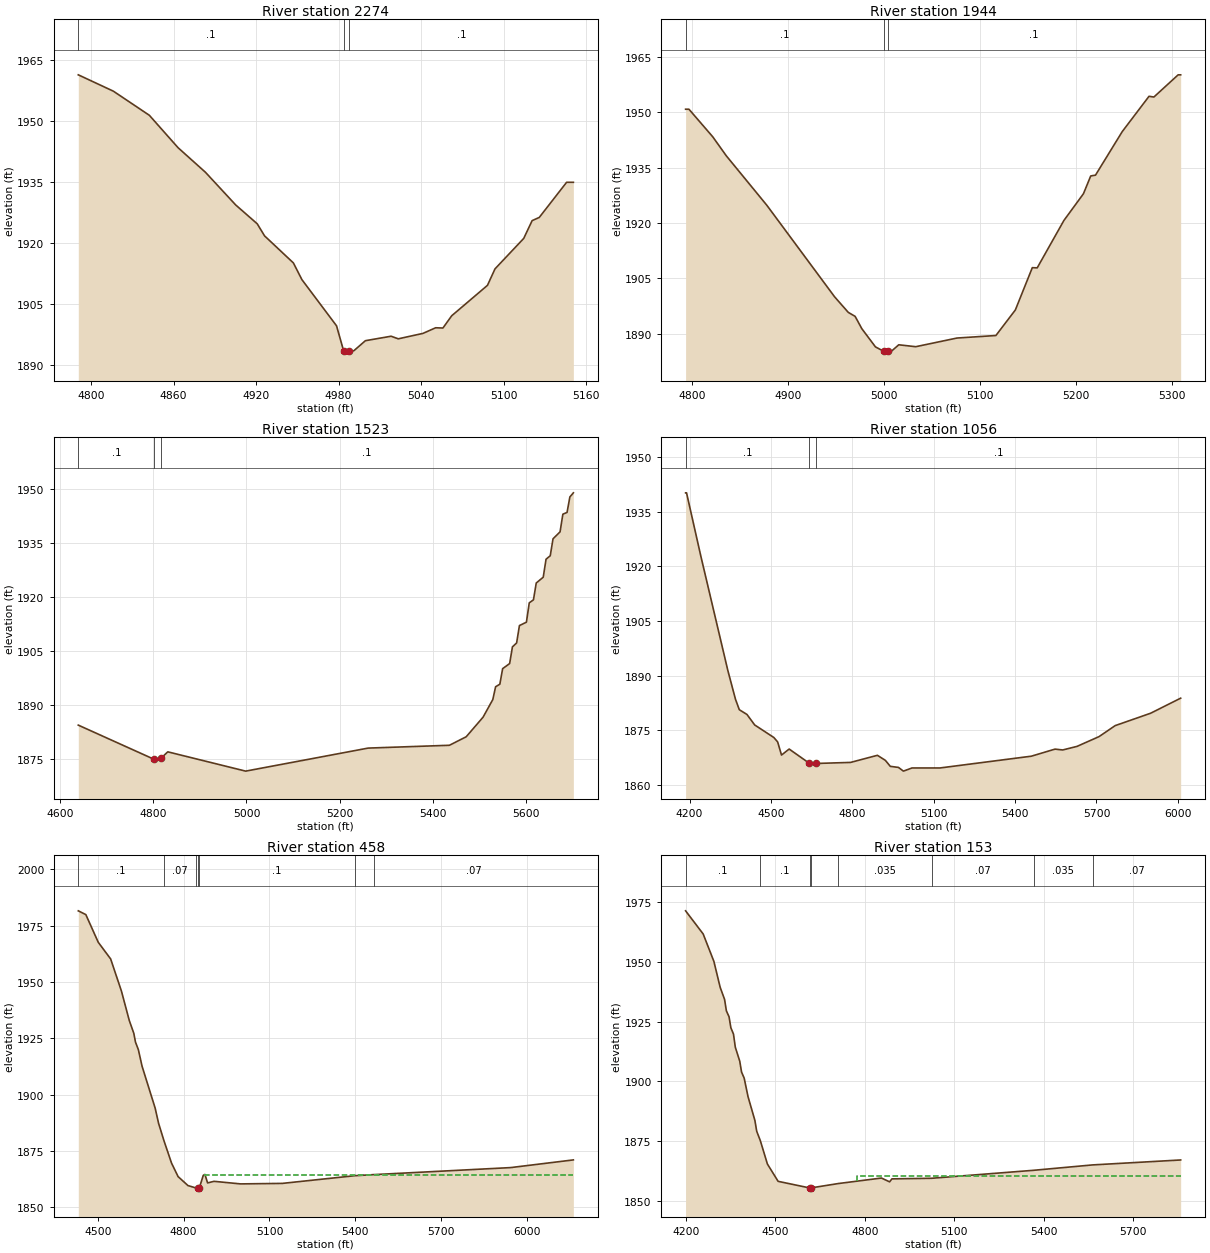
Type RM Length L Ch R = 1 ,2274    ,330,330,330
BEGIN DESCRIPTION:
Stream0422 4.0
END DESCRIPTION:
XS GIS Cut Line= 2
       1871168.9     13967075.69      1871061.26     13967419.43
#Sta/Elev= 30
  4790.6 1961.39  4816.1 1957.37  4842.3 1951.43  4863.2 1943.45  4883.1 1937.41
  4905.1 1929.37  4920.8 1924.72  4926.1 1921.76  4947.1 1915.09  4953.3 1910.98
  4978.5 1899.61  4983.7 1893.39    4984 1892.89  4987.5 1892.89  4987.7 1893.39
    4991 1893.45  4999.5 1895.95  5018.2 1897.05  5023.4 1896.41  5041.4 1897.75
  5050.6 1899.13  5055.9 1899.07  5062.3 1902.09  5088.3 1909.57  5093.8 1913.63
  5114.7 1921.13  5120.8  1925.5    5126 1926.29  5145.9 1934.94  5150.8 1934.94
#Mann= 3 ,-1 , 0
  4790.6      .1       0  4983.7     .05       0  4987.7      .1       0
Bank Sta=4983.7,4987.7
XS Rating Curve= 0 ,0
Exp/Cntr=0.3,0.1

Type RM Length L Ch R = 1 ,1944    ,421,421,421
BEGIN DESCRIPTION:
Stream0422 3.0
END DESCRIPTION:
XS GIS Cut Line= 3
      1870974.99     13966975.01        1870825.       13967125.
      1870875.01     13967425.05
#Sta/Elev= 30
  4792.9 1950.85  4796.4 1950.85  4821.2 1943.39  4835.3 1938.25  4877.7 1924.81
  4948.4    1900  4962.6 1895.81  4969.7 1894.74  4976.7  1891.4  4990.9 1886.47
  4999.5 1885.28  4999.7 1884.78  5003.5 1885.28  5007.5 1885.28  5015.2 1887.04
  5032.9 1886.52    5076 1888.87  5116.5 1889.55  5136.8 1896.47  5154.5 1907.93
  5159.6 1907.88  5187.5 1920.74  5207.8 1927.95  5215.4 1932.77  5220.4    1933
  5248.3  1944.8  5276.2 1954.35  5281.3 1954.16  5306.6 1960.17  5309.2 1960.17
#Mann= 3 ,-1 , 0
  4792.9      .1       0  4999.5     .05       0  5003.5      .1       0
Bank Sta=4999.5,5003.5
XS Rating Curve= 0 ,0
Exp/Cntr=0.3,0.1

Type RM Length L Ch R = 1 ,1523    ,467,467,467
BEGIN DESCRIPTION:
Stream0422 2.0
END DESCRIPTION:
XS GIS Cut Line= 4
      1870674.97     13966775.03      1870438.24      13966972.3
      1870440.66      13967123.5        1870775.       13967625.
#Sta/Elev= 30
  4639.2 1884.49  4802.5 1874.97  4816.8 1875.32  4831.2 1877.08  4998.3 1871.73
  5261.1 1878.12  5435.4  1878.9  5471.4 1881.26  5507.5 1886.68  5528.5 1891.58
  5534.5 1895.14  5543.6 1895.84  5549.6 1900.16  5564.6 1901.57  5570.6  1906.2
  5579.6 1907.29  5585.6 1912.11  5600.6 1913.04  5606.7 1918.41  5615.7 1919.25
  5621.7 1923.92  5636.7 1925.53  5642.7 1930.51  5651.7 1931.47  5657.7 1936.18
  5672.8 1938.11  5678.8 1943.01  5687.8 1943.49  5693.8 1947.78  5701.3 1948.93
#Mann= 3 ,-1 , 0
  4639.2      .1       0  4802.5     .05       0  4816.8      .1       0
#Block Obstruct= 2 , 0
                         4830.98         1877.03
Bank Sta=4802.5,4816.8
XS Rating Curve= 0 ,0
Exp/Cntr=0.3,0.1

Type RM Length L Ch R = 1 ,1056    ,598,598,598
BEGIN DESCRIPTION:
Stream0422 1.0
END DESCRIPTION:
XS GIS Cut Line= 4
        1870525.       13966425.      1870006.67     13966943.33
      1869999.58     13967159.24      1870425.02     13967925.03
#Sta/Elev= 30
  4185.2 1940.16  4188.7 1940.16  4241.8 1922.65  4340.8 1891.45  4369.1 1883.51
  4383.2 1880.64  4411.5 1879.33  4439.8 1876.46  4510.5 1873.01  4524.6 1871.79
  4538.8 1868.19    4567 1869.84 4641.46 1865.93    4666 1865.88  4793.3 1866.17
  4892.3 1868.12  4921.6 1866.74  4939.9 1865.09  4969.9  1864.8  4988.2 1863.78
    5020 1864.65  5123.2 1864.65    5460 1867.88    5547 1869.82  5575.6 1869.59
  5628.2 1870.57  5709.4 1873.25  5768.9 1876.27  5899.3 1879.66  6010.3  1883.8
#Mann= 3 ,-1 , 0
  4185.2      .1       0 4641.46     .05       0    4666      .1       0
#Block Obstruct= 2 , 0
                         4888.82         1868.09
Bank Sta=4641.46,4666
XS Rating Curve= 0 ,0
Exp/Cntr=0.3,0.1

Type RM Length L Ch R = 1 ,458     ,305,305,305
BEGIN DESCRIPTION:
Stream0422 0.0
END DESCRIPTION:
XS GIS Cut Line= 4
      1869944.95     13966130.52      1869605.47     13966735.74
      1869682.71     13967235.55      1869968.31     13967684.42
#Sta/Elev= 30
  4431.4 1981.57  4457.8 1979.89  4501.2 1967.62  4544.6 1960.22  4582.2 1946.01
  4609.7 1932.94  4625.6 1927.23  4631.5 1923.31  4641.6 1919.94  4654.4 1912.67
  4700.3 1894.03  4712.3 1887.28  4731.3  1879.5  4757.6 1869.65  4780.5 1863.67
    4815 1859.69  4842.1 1858.66  4850.7 1858.61  4850.9 1858.11  4854.7 1858.61
  4868.6 1864.24  4874.4 1864.61  4883.7 1860.87  4906.3 1861.57  4998.8 1860.43
  5144.8 1860.65  5398.3 1864.06  5464.8 1864.54  5943.6 1867.66  6163.1 1871.07
#Mann= 7 ,-1 , 0
  4431.4      .1       0  4731.3     .07       0  4842.1      .1       0
  4850.7     .05       0  4854.7      .1       0  5398.3    .035       0
  5464.8     .07       0
#XS Ineff= 2 , 0
                         4872.22         1864.48
Permanent Ineff=
       F       F
Bank Sta=4850.7,4854.7
XS Rating Curve= 0 ,0
Exp/Cntr=0.3,0.1

Type RM Length L Ch R = 1 ,153     ,0,0,0
BEGIN DESCRIPTION:
Stream0422 0.1
END DESCRIPTION:
XS GIS Cut Line= 4
      1869723.67     13965961.89      1869331.31     13966538.28
      1869459.78     13966923.69      1869706.31      13967423.7
#Sta/Elev= 30
  4198.9 1971.36  4257.9 1961.67  4293.8 1950.22  4314.8  1939.4  4329.7 1934.28
  4335.8  1929.5  4344.7 1927.03  4350.7 1922.46  4359.6 1919.77  4365.7 1914.29
  4380.6 1908.45  4386.6 1903.92  4395.5 1901.34  4408.3 1893.64  4431.4 1883.65
  4437.5 1879.12  4449.6  1875.2  4473.4 1865.41  4509.3 1858.16  4615.1  1855.4
  4615.3  1854.9  4619.1  1855.4  4710.4 1857.22  4855.9 1859.54  4883.4 1857.95
  4891.1 1859.19  5024.5 1859.44  5366.8 1862.78  5564.4 1865.03  5859.9  1867.1
#Mann= 8 ,-1 , 0
  4198.9      .1       0  4449.6      .1       0  4615.1     .05       0
  4619.1      .1       0  4710.4    .035       0  5024.5     .07       0
  5366.8    .035       0  5564.4     .07       0
#XS Ineff= 2 , 0
                         4774.89         1860.23
Permanent Ineff=
       F       F
#Block Obstruct= 2 , 0
                         4862.63         1859.56
Bank Sta=4615.1,4619.1
XS Rating Curve= 0 ,0
Exp/Cntr=0.3,0.1

Chan Stop Cuts=-1
Use User Specified Reach Order=0
Composite Channel Slope=5