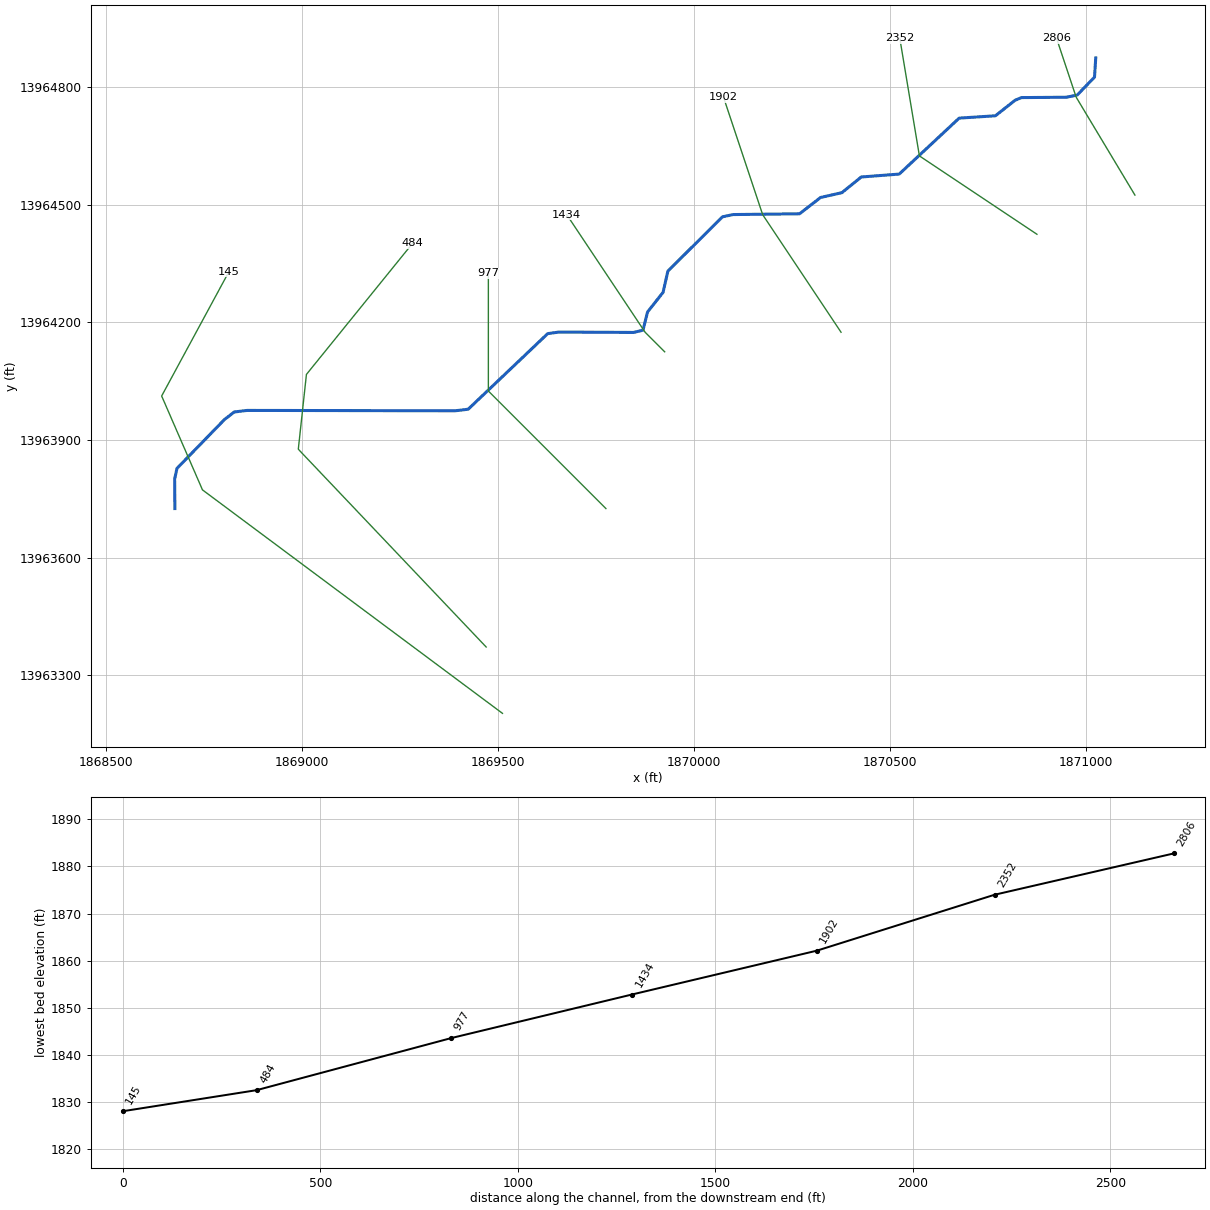
--- Stream0423.prj (project) ---

Proj Title=Stream0423 Base Level Engineering
Current Plan=p01
Default Exp/Contr=0.3,0.1
English Units
Geom File=g01
Flow File=f01
Plan File=p01
Y Axis Title=Elevation
X Axis Title(PF)=Main Channel Distance
X Axis Title(XS)=Station
BEGIN DESCRIPTION:
Stream0423
END DESCRIPTION:
DSS Export Rating Curves= 0
DSS Export Rating Curve Sorted= 0
DSS Export Volume Flow Curves= 0
DXF OffsetX= 0
DXF OffsetY= 0
DXF ScaleX= 1
DXF ScaleY= 10

--- Stream0423.p01 (plan) ---

Plan Title=Multiple Run
Short Identifier=Multiple
Geom File=g01
Flow File=f01
Subcritical Flow
K Sum by GR= 0
Std Step Tol= 0.01
Critical Tol= 0.01
Num of Std Step Trials= 20
Max Error Tol= 0.3
Flow Tol Ratio= 0.001
Split Flow NTrial= 30
Split Flow Tol= 0.02
Split Flow Ratio= 0.02
Log Output Level= 0
Friction Slope Method= 1
Unsteady Friction Slope Method= 2
Unsteady Bridges Friction Slope Method= 1
Parabolic Critical Depth
Global Vel Dist=  1 , 1 , 1
Global Log Level= 0
CheckData=True
Encroach Param= -1, 0, 0, 0
BEGIN DESCRIPTION:
Multiple Run
END DESCRIPTION:

--- Stream0423.f01 (steady flow) ---

Flow Title=Multiple
Number of Profiles=7
Profile Names=10-year,25-year,50-year,1pct_min,100-year,1pct_plu,500-year
River Rch & RM= Stream0423,Reach-1,2806
     711    1185    1628    1084    2163    4316    3765
Boundary for River Rch & Prof#=Stream0423,Reach-1,1
Up Type=0
Dn Type=3
Dn Slope=0.005
Boundary for River Rch & Prof#=Stream0423,Reach-1,2
Up Type=0
Dn Type=3
Dn Slope=0.005
Boundary for River Rch & Prof#=Stream0423,Reach-1,3
Up Type=0
Dn Type=3
Dn Slope=0.005
Boundary for River Rch & Prof#=Stream0423,Reach-1,4
Up Type=0
Dn Type=3
Dn Slope=0.005
Boundary for River Rch & Prof#=Stream0423,Reach-1,5
Up Type=0
Dn Type=3
Dn Slope=0.005
Boundary for River Rch & Prof#=Stream0423,Reach-1,6
Up Type=0
Dn Type=3
Dn Slope=0.005
Boundary for River Rch & Prof#=Stream0423,Reach-1,7
Up Type=0
Dn Type=3
Dn Slope=0.005

--- Stream0423.g01 (geometry) ---

Geom Title=Existing Conditions
Program Version=4.10

River Reach=Stream0423      ,Reach-1
Reach XY= 30
        1871025.       13964875.      1871021.88     13964825.98
      1870977.69     13964780.27      1870950.18      13964774.7
      1870835.51     13964773.77      1870818.94     13964766.86
      1870769.02     13964727.36       1870676.5     13964721.39
       1870523.5     13964578.61      1870426.59     13964571.17
      1870377.18     13964531.11      1870322.82     13964518.88
      1870269.07     13964477.24      1870099.88     13964475.29
      1870072.55     13964469.54      1869933.14     13964331.05
      1869920.82      13964276.7      1869881.27     13964226.79
      1869869.59     13964180.17      1869845.44     13964174.46
      1869654.82     13964175.43      1869626.46     13964171.46
      1869423.54     13963978.54       1869390.2     13963974.51
       1868859.8     13963975.49      1868826.46     13963971.46
      1868801.47     13963952.14      1868680.35      13963827.5
       1868674.4     13963800.25        1868675.       13963725.

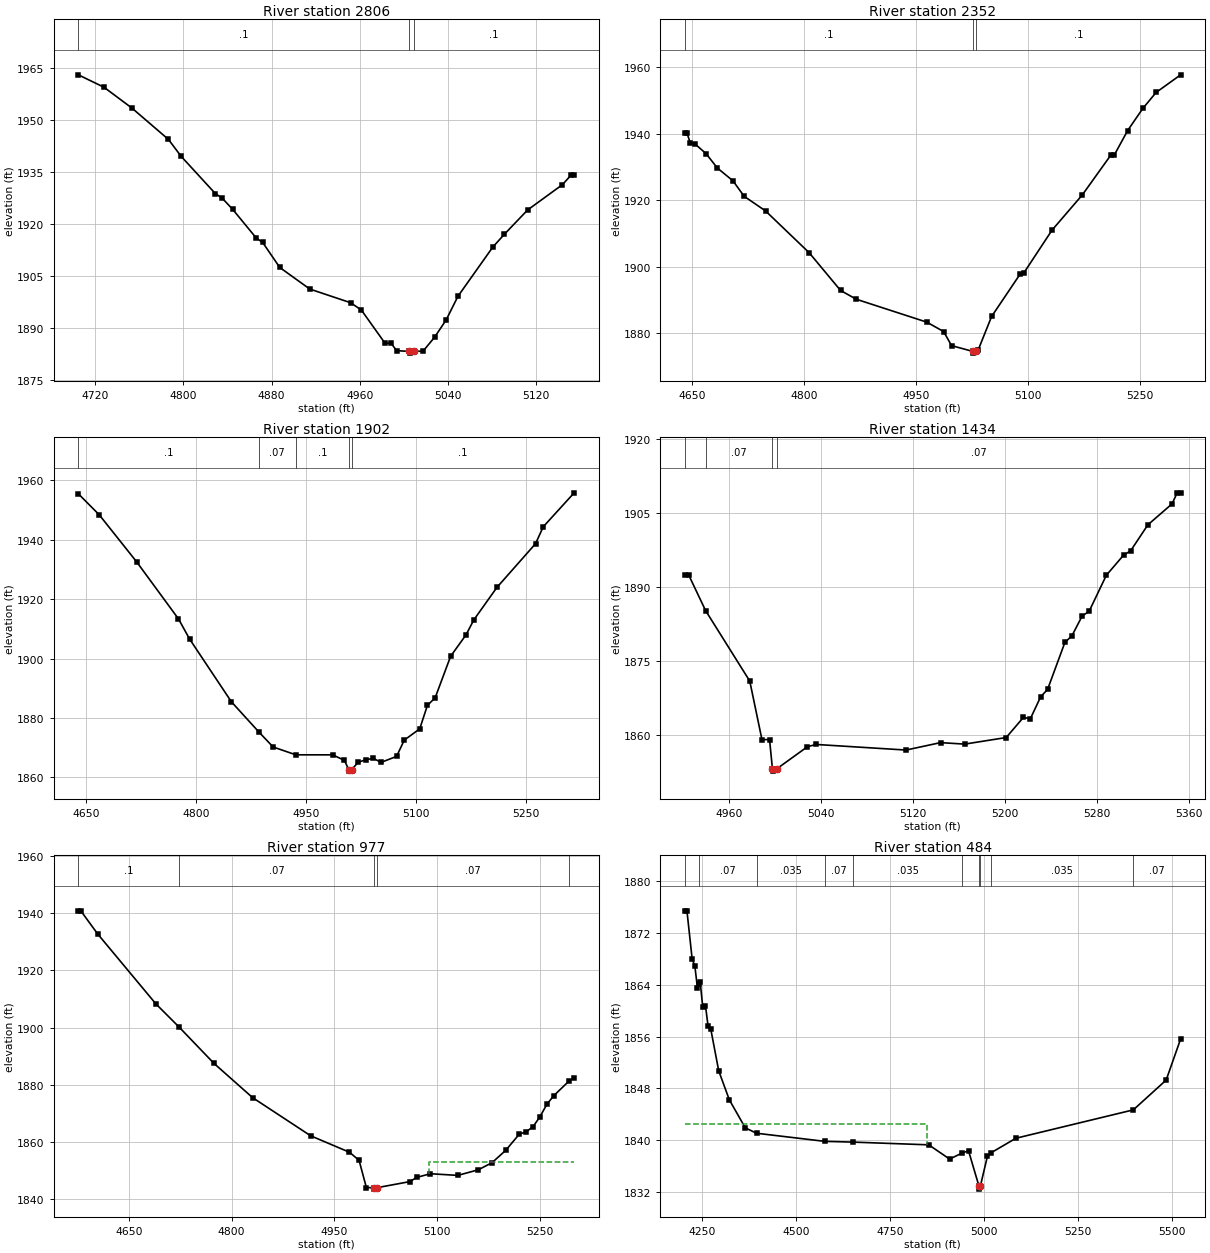
Type RM Length L Ch R = 1 ,2806    ,454,454,454
BEGIN DESCRIPTION:
Stream0423 5.0
END DESCRIPTION:
XS GIS Cut Line= 3
      1871125.01     13964524.98        1870975.       13964775.
        1870925.     13964925.01
#Sta/Elev= 30
  4704.8 1963.16  4728.1 1959.57  4753.4 1953.56  4786.5 1944.51  4798.1  1939.6
  4829.2 1928.81  4835.1  1927.6  4844.8  1924.3  4866.1 1916.05    4872 1914.74
  4887.5 1907.52  4914.7 1901.29  4951.7 1897.34  4961.4 1895.27  4982.8 1885.71
  4988.6 1885.58  4993.5 1883.49  5004.9 1883.28  5005.2 1882.78  5008.9 1883.28
  5017.5 1883.36    5028 1887.41  5038.5 1892.42  5049.1  1899.2  5080.7  1913.4
  5091.2 1917.11  5112.3 1924.13  5143.9 1931.45  5151.9 1934.26  5154.5 1934.26
#Mann= 3 ,-1 , 0
  4704.8      .1       0  5004.9     .05       0  5008.9      .1       0
Bank Sta=5004.9,5008.9
XS Rating Curve= 0 ,0
Exp/Cntr=0.3,0.1

Type RM Length L Ch R = 1 ,2352    ,450,450,450
BEGIN DESCRIPTION:
Stream0423 4.0
END DESCRIPTION:
XS GIS Cut Line= 3
      1870875.01     13964424.99        1870575.       13964625.
        1870525.     13964924.99
#Sta/Elev= 30
  4639.7 1940.18  4642.7 1940.18  4647.2 1937.16  4653.2    1937  4668.3 1934.02
  4683.3 1929.73  4704.3 1925.85  4719.3 1921.19  4747.9 1916.81  4806.5  1904.2
  4848.5 1892.86  4869.6 1890.21  4964.2 1883.31  4986.7 1880.48  4997.3 1876.25
  5026.1 1874.49  5026.4 1873.99  5030.1 1874.49  5033.2 1875.04    5051 1885.02
    5089  1897.7    5094 1898.06  5132.1 1911.04  5172.6 1921.62  5210.6 1933.53
  5215.7 1933.72  5233.4    1941  5253.7 1947.64  5271.5 1952.46  5304.4 1957.77
#Mann= 3 ,-1 , 0
  4639.7      .1       0  5026.1     .05       0  5030.1      .1       0
Bank Sta=5026.1,5030.1
XS Rating Curve= 0 ,0
Exp/Cntr=0.3,0.1

Type RM Length L Ch R = 1 ,1902    ,468,468,468
BEGIN DESCRIPTION:
Stream0423 3.0
END DESCRIPTION:
XS GIS Cut Line= 3
      1870375.02     13964174.97        1870175.       13964475.
        1870075.     13964774.99
#Sta/Elev= 30
  4639.4 1955.45    4668 1948.35  4719.1 1932.51  4776.1 1913.33  4791.2 1906.59
  4848.3 1885.45  4885.4 1875.39  4905.3 1870.22  4936.3 1867.59  4986.5 1867.58
  5002.6 1865.73  5008.5  1862.6  5008.8  1862.1  5012.5  1862.6  5021.1 1865.02
  5031.6 1865.95  5042.1 1866.38  5052.7 1865.05  5073.8 1867.06  5084.3 1872.54
  5105.4 1876.33  5115.9 1884.23  5126.5 1886.81  5147.6 1900.77  5168.6 1907.97
  5179.2 1912.99  5210.8 1923.94  5263.5 1938.66    5274 1944.34  5316.2 1955.77
#Mann= 5 ,-1 , 0
  4639.4      .1       0  4885.4     .07       0  4936.3      .1       0
  5008.5     .05       0  5012.5      .1       0
Bank Sta=5008.5,5012.5
XS Rating Curve= 0 ,0
Exp/Cntr=0.3,0.1

Type RM Length L Ch R = 1 ,1434    ,457,457,457
BEGIN DESCRIPTION:
Stream0423 2.0
END DESCRIPTION:
XS GIS Cut Line= 3
      1869924.97     13964125.03        1869875.       13964175.
      1869675.01     13964474.98
#Sta/Elev= 30
  4921.4 1892.37  4924.9 1892.37  4939.5 1885.22  4977.9 1870.98  4988.5 1859.15
  4995.1 1859.15  4997.6 1853.28  4997.8 1852.78  5001.6 1853.28  5028.1 1857.72
  5035.6 1858.17  5113.8 1857.04  5143.8 1858.54  5164.8 1858.24  5200.9 1859.57
  5215.9 1863.64  5221.9 1863.36  5230.9 1867.81  5236.9  1869.3    5252 1878.82
    5258  1880.1    5267 1884.15    5273 1885.07    5288 1892.37    5303 1896.44
  5309.1  1897.3  5324.1 1902.56  5345.1 1906.79  5349.6 1909.03  5352.6 1909.03
#Mann= 4 ,-1 , 0
  4921.4      .1       0  4939.5     .07       0  4997.6     .05       0
  5001.6     .07       0
Bank Sta=4997.6,5001.6
XS Rating Curve= 0 ,0
Exp/Cntr=0.3,0.1

Type RM Length L Ch R = 1 ,977     ,493,493,493
BEGIN DESCRIPTION:
Stream0423 1.0
END DESCRIPTION:
XS GIS Cut Line= 3
      1869775.02     13963724.98        1869475.       13964025.
        1869475.     13964325.01
#Sta/Elev= 30
    4576  1940.8  4579.6  1940.8  4604.3  1932.7  4689.2  1908.3    4723 1900.22
    4774 1887.51  4830.6  1875.5  4915.4 1862.17    4972 1856.43  4986.1  1853.6
  4996.8 1844.05  5008.3 1844.03  5008.5 1843.53    5012 1843.53  5012.3 1844.03
  5060.3 1846.16  5070.3 1847.63  5090.3 1848.91  5130.3 1848.33  5160.3 1850.29
  5180.3 1852.77  5200.3 1857.08  5220.3 1862.78  5230.3 1863.57  5240.3 1865.38
  5250.3  1868.8  5260.3 1873.13  5270.3 1876.13  5293.3 1881.42  5300.3 1882.47
#Mann= 5 ,-1 , 0
    4576      .1       0    4723     .07       0  5008.3     .05       0
  5012.3     .07       0  5293.3      .1       0
#XS Ineff= 2 , 0
                         5088.37          1852.9
Permanent Ineff=
       F       F
Bank Sta=5008.3,5012.3
XS Rating Curve= 0 ,0
Exp/Cntr=0.3,0.1

Type RM Length L Ch R = 1 ,484     ,339,339,339
BEGIN DESCRIPTION:
Stream0423 0.0
END DESCRIPTION:
XS GIS Cut Line= 4
      1869469.41     13963371.69      1868989.99     13963876.47
       1869010.7     13964067.32       1869282.1     13964402.48
#Sta/Elev= 30
  4204.7 1875.43  4210.4 1875.43  4224.2 1868.02  4231.4 1866.93  4238.3 1863.56
  4242.5 1864.11  4245.6 1864.51  4252.5 1860.51  4259.7  1860.8  4266.6 1857.63
  4273.9 1857.15  4294.9 1850.73  4323.3 1846.23  4365.7 1841.91  4395.7 1841.08
  4576.8 1839.83  4653.5 1839.71  4853.9 1839.29  4909.4 1837.09  4943.1 1838.04
  4959.7 1838.37  4987.3 1832.95  4987.5 1832.45  4991.3 1832.95    5010 1837.53
  5018.6 1838.03  5085.9 1840.31  5398.2 1844.69  5485.6 1849.29  5524.1 1855.64
#Mann= 10 ,-1 , 0
  4204.7      .1       0  4242.5     .07       0  4395.7    .035       0
  4576.8     .07       0  4653.5    .035       0  4943.1     .07       0
  4987.3     .05       0  4991.3     .07       0  5018.6    .035       0
  5398.2     .07       0
#XS Ineff= 2 , 0
         4849.35 1842.46
Permanent Ineff=
       F       F
Bank Sta=4987.3,4991.3
XS Rating Curve= 0 ,0
Exp/Cntr=0.3,0.1

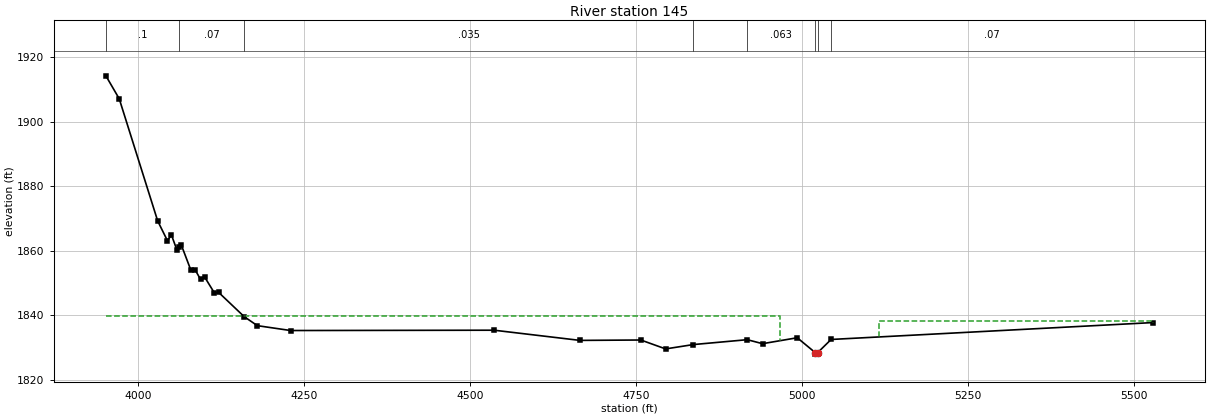
Type RM Length L Ch R = 1 ,145     ,0,0,0
BEGIN DESCRIPTION:
Stream0423 0.1
END DESCRIPTION:
XS GIS Cut Line= 4
      1869511.09     13963202.33      1868745.43     13963772.67
      1868641.26     13964012.26      1868813.13     13964329.96
#Sta/Elev= 30
  3951.5 1914.29  3971.6 1907.16  4029.5 1869.28  4044.1 1863.18  4050.3 1864.89
  4058.7 1860.13  4062.1 1861.11  4064.9 1861.92  4079.5    1854  4085.8 1854.16
  4094.1 1851.12  4100.4 1851.82    4115 1846.92  4121.2 1847.14  4159.8 1839.59
  4179.6  1836.8  4229.7 1835.29  4536.2 1835.39  4665.5 1832.23  4757.2 1832.35
  4794.5 1829.59  4836.5 1830.94  4917.5 1832.45  4940.5 1831.21  4992.8 1833.05
  5019.7 1828.47    5020 1827.97  5023.7 1828.47  5043.8 1832.52  5528.7 1837.76
#Mann= 8 ,-1 , 0
  3951.5      .1       0  4062.1     .07       0  4159.8    .035       0
  4836.5     .07       0  4917.5    .063       0  5019.7     .05       0
  5023.7    .063       0  5043.8     .07       0
#XS Ineff= 2 , 0
         4967.44 1839.87 5116.28         1838.24
Permanent Ineff=
       F       F
Bank Sta=5019.7,5023.7
XS Rating Curve= 0 ,0
Exp/Cntr=0.3,0.1

Chan Stop Cuts=-1
Use User Specified Reach Order=0
Composite Channel Slope=5