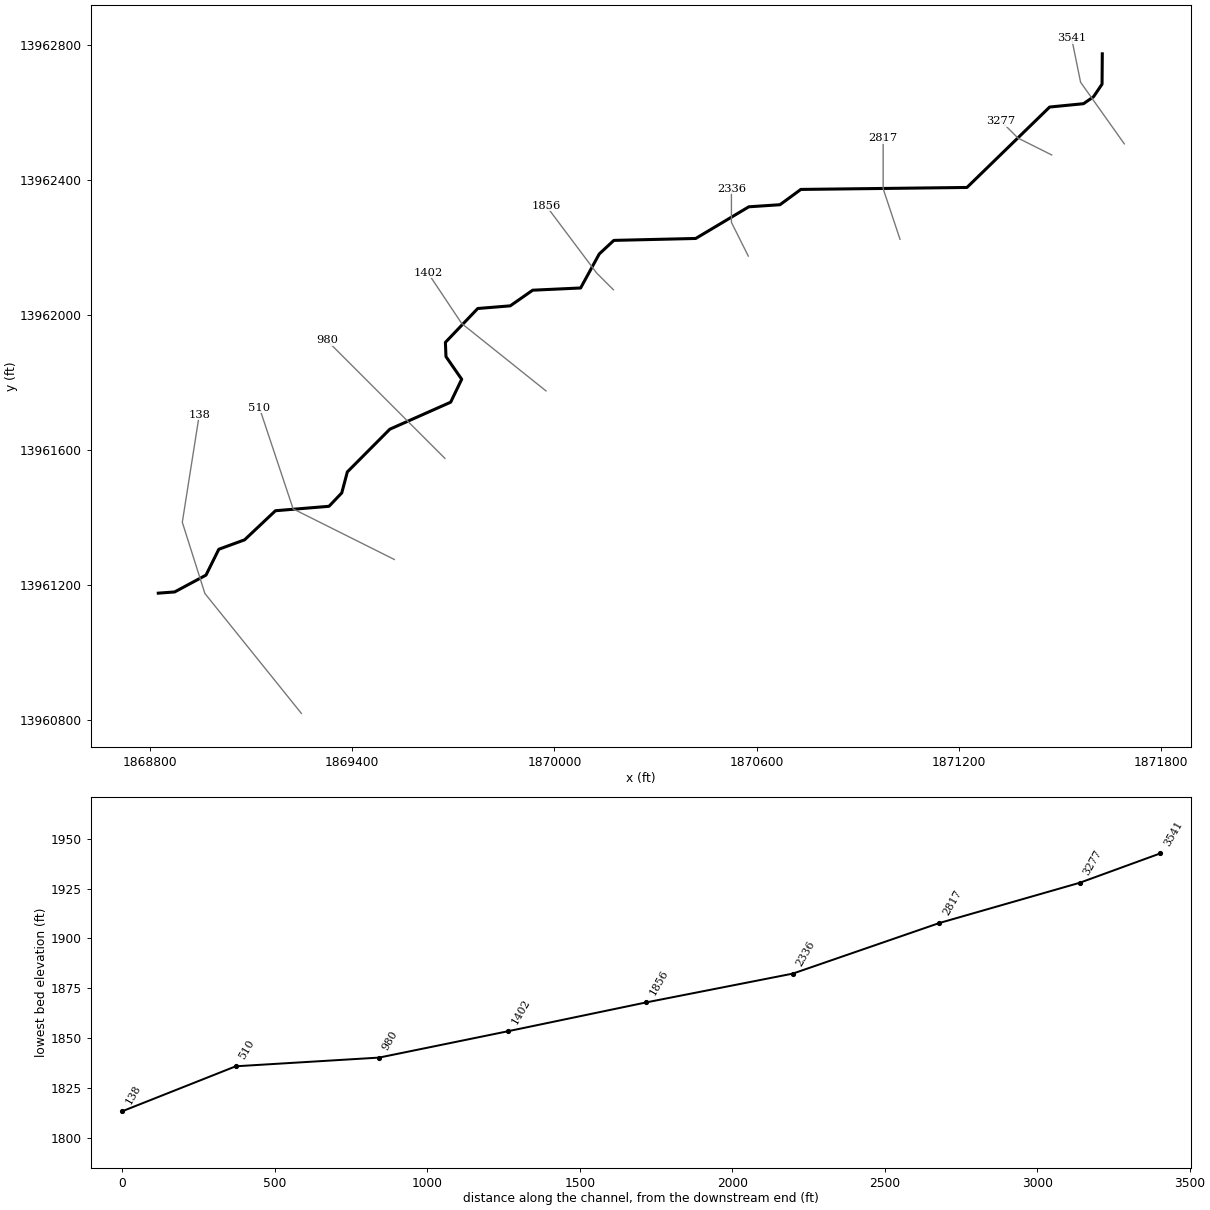
--- Stream0424.prj (project) ---

Proj Title=Stream0424 Base Level Engineering
Current Plan=p01
Default Exp/Contr=0.3,0.1
English Units
Geom File=g01
Flow File=f01
Plan File=p01
Y Axis Title=Elevation
X Axis Title(PF)=Main Channel Distance
X Axis Title(XS)=Station
BEGIN DESCRIPTION:
Stream0424
END DESCRIPTION:
DSS Export Rating Curves= 0
DSS Export Rating Curve Sorted= 0
DSS Export Volume Flow Curves= 0
DXF OffsetX= 0
DXF OffsetY= 0
DXF ScaleX= 1
DXF ScaleY= 10

--- Stream0424.p01 (plan) ---

Plan Title=Multiple Run
Short Identifier=Multiple
Geom File=g01
Flow File=f01
Subcritical Flow
K Sum by GR= 0
Std Step Tol= 0.01
Critical Tol= 0.01
Num of Std Step Trials= 20
Max Error Tol= 0.3
Flow Tol Ratio= 0.001
Split Flow NTrial= 30
Split Flow Tol= 0.02
Split Flow Ratio= 0.02
Log Output Level= 0
Friction Slope Method= 1
Unsteady Friction Slope Method= 2
Unsteady Bridges Friction Slope Method= 1
Parabolic Critical Depth
Global Vel Dist=  1 , 1 , 1
Global Log Level= 0
CheckData=True
Encroach Param= -1, 0, 0, 0
BEGIN DESCRIPTION:
Multiple Run
END DESCRIPTION:

--- Stream0424.f01 (steady flow) ---

Flow Title=Multiple
Program Version=4.10
Number of Profiles= 7
Profile Names=10-year,25-year,50-year,1pct_min,100-year,1pct_plu,500-year
River Rch & RM=Stream0424,Reach-1         ,3541
     537     880    1197     790    1576    3144    2692
Boundary for River Rch & Prof#=Stream0424,Reach-1         , 1
Up Type= 0
Dn Type= 3
Dn Slope=0.01
Boundary for River Rch & Prof#=Stream0424,Reach-1         , 2
Up Type= 0
Dn Type= 3
Dn Slope=0.01
Boundary for River Rch & Prof#=Stream0424,Reach-1         , 3
Up Type= 0
Dn Type= 3
Dn Slope=0.01
Boundary for River Rch & Prof#=Stream0424,Reach-1         , 4
Up Type= 0
Dn Type= 3
Dn Slope=0.01
Boundary for River Rch & Prof#=Stream0424,Reach-1         , 5
Up Type= 0
Dn Type= 3
Dn Slope=0.01
Boundary for River Rch & Prof#=Stream0424,Reach-1         , 6
Up Type= 0
Dn Type= 3
Dn Slope=0.01
Boundary for River Rch & Prof#=Stream0424,Reach-1         , 7
Up Type= 0
Dn Type= 3
Dn Slope=0.01
DSS Import GetInterval= 0
DSS Import GetPeak= 0
DSS Import FillOption= 0

--- Stream0424.g01 (geometry) ---

Geom Title=Existing Conditions

River Reach=Stream0424,Reach-1
Reach XY= 30
      1871625.00     13962775.00      1871624.27     13962685.13
      1871599.02     13962647.63      1871569.31     13962627.06
      1871468.83     13962617.14      1871223.54     13962378.54
      1870730.94     13962372.74      1870669.02     13962327.36
      1870576.58     13962321.17      1870419.07     13962227.24
      1870176.25     13962221.55      1870133.03     13962181.36
      1870077.70     13962080.36      1869935.51     13962073.77
      1869869.02     13962027.36      1869772.56     13962019.48
      1869676.62     13961918.97      1869678.37     13961876.74
      1869724.98     13961809.53      1869692.23     13961741.49
      1869511.78     13961661.38      1869385.79     13961534.66
      1869369.26     13961472.43      1869331.47     13961432.70
      1869172.56     13961419.52      1869081.02     13961333.18
      1869004.57     13961305.27      1868966.53     13961228.51
      1868873.55     13961178.58      1868825.00     13961175.00

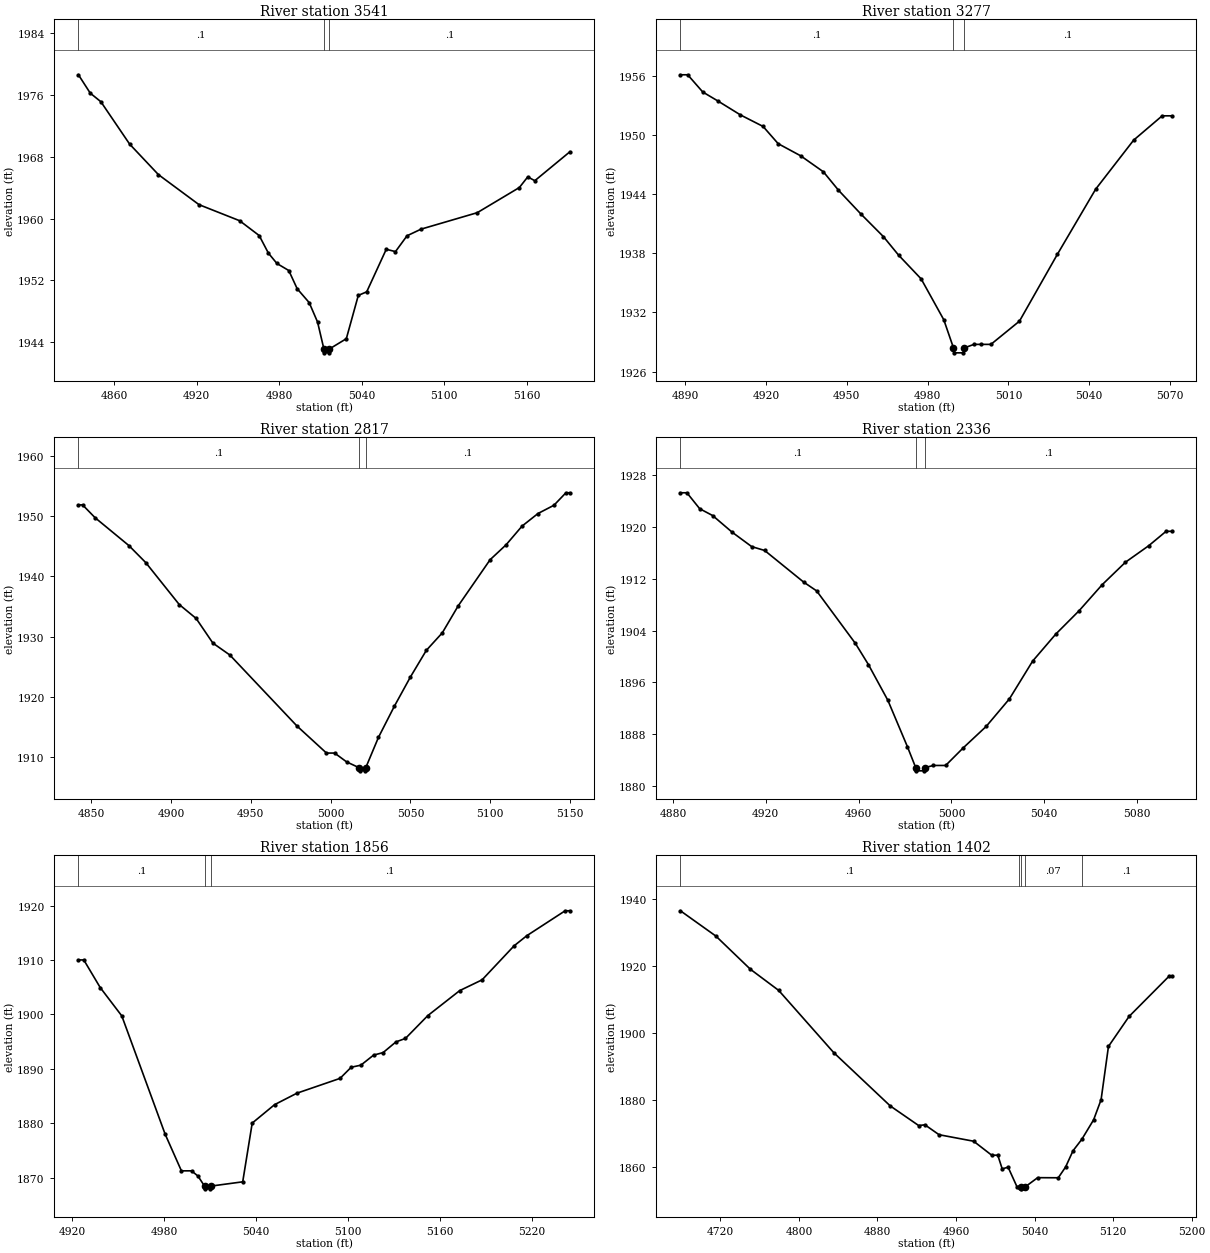
Type RM Length L Ch R = 1,3541,264,264,264
BEGIN DESCRIPTION:
Stream0424 8.0
END DESCRIPTION:
XS GIS Cut Line= 3
      1871690.28     13962507.96      1871560.60     13962690.68
      1871534.12     13962820.96
#Sta/Elev= 30
  4834.2 1978.63  4842.8 1976.25  4850.5 1975.14  4871.4 1969.65  4892.3 1965.70
  4921.8 1961.81  4951.3 1959.73  4965.5 1957.81  4972.2 1955.53  4978.4 1954.19
  4987.0 1953.28  4993.1 1950.92  5001.8 1949.13  5007.9 1946.61  5012.5 1943.12
  5012.8 1942.62  5016.3 1942.62  5016.5 1943.12  5028.8 1944.45  5037.5 1950.06
  5043.6 1950.52  5057.8 1956.03  5064.5 1955.73  5072.9 1957.78  5083.1 1958.64
  5123.9 1960.77  5154.5 1964.03  5160.6 1965.41  5165.7 1964.91  5191.2 1968.66
#Mann=3,-1,0
  4834.2     0.1       0  5012.5    0.05       0  5016.5     0.1       0
Bank Sta=5012.5,5016.5
Exp/Cntr=0.3,0.1

Type RM Length L Ch R = 1,3277,460,460,460
BEGIN DESCRIPTION:
Stream0424 7.0
END DESCRIPTION:
XS GIS Cut Line= 3
      1871474.96     13962475.02      1871375.00     13962525.00
      1871324.98     13962575.02
#Sta/Elev= 28
  4888.2 1956.15  4890.9 1956.15  4896.5 1954.40  4902.1 1953.49  4910.5 1952.07
  4918.9 1950.90  4924.5 1949.15  4932.9 1947.91  4941.3 1946.29  4946.9 1944.42
  4955.2 1942.01  4963.6 1939.70  4969.2 1937.83  4977.6 1935.41  4986.0 1931.26
  4989.6 1928.40  4989.8 1927.90  4993.3 1927.90  4993.6 1928.40  4997.2 1928.76
  5000.0 1928.76  5003.5 1928.76  5014.1 1931.12  5028.2 1937.92  5042.4 1944.53
  5056.5 1949.51  5067.1 1951.98  5070.7 1951.98
#Mann=3,-1,0
  4888.2     0.1       0  4989.6    0.05       0  4993.6     0.1       0
Bank Sta=4989.6,4993.6
Exp/Cntr=0.3,0.1

Type RM Length L Ch R = 1,2817,481,481,481
BEGIN DESCRIPTION:
Stream0424 6.0
END DESCRIPTION:
XS GIS Cut Line= 3
      1871025.00     13962225.00      1870975.00     13962375.00
      1870975.00     13962524.99
#Sta/Elev= 30
  4841.9 1951.85  4844.5 1951.85  4852.4 1949.71  4873.5 1945.11  4884.1 1942.28
  4905.1 1935.32  4915.7 1933.01  4926.2 1928.92  4936.8 1926.95  4978.9 1915.17
  4997.4 1910.68  5002.5 1910.68  5010.0 1909.22  5018.0 1908.23  5018.3 1907.73
  5021.8 1907.73  5022.0 1908.23  5030.0 1913.29  5040.0 1918.47  5050.0 1923.29
  5060.0 1927.72  5070.0 1930.62  5080.0 1935.11  5100.0 1942.76  5110.0 1945.23
  5120.0 1948.33  5130.0 1950.42  5140.0 1951.79  5147.5 1953.86  5150.0 1953.86
#Mann=3,-1,0
  4841.9     0.1       0  5018.0    0.05       0  5022.0     0.1       0
Bank Sta=5018,5022
Exp/Cntr=0.3,0.1

Type RM Length L Ch R = 1,2336,480,480,480
BEGIN DESCRIPTION:
Stream0424 5.0
END DESCRIPTION:
XS GIS Cut Line= 3
      1870574.98     13962175.04      1870525.00     13962275.00
      1870525.00     13962375.04
#Sta/Elev= 30
  4883.2 1925.28  4886.0 1925.28  4891.5 1922.82  4897.1 1921.76  4905.5 1919.19
  4913.9 1916.97  4919.5 1916.37  4936.3 1911.49  4941.9 1910.13  4958.6 1902.02
  4964.2 1898.76  4972.6 1893.23  4981.0 1886.09  4984.6 1882.84  4984.8 1882.34
  4988.3 1882.34  4988.6 1882.84  4992.2 1883.17  4997.5 1883.17  5005.0 1885.86
  5015.0 1889.21  5025.0 1893.46  5035.0 1899.29  5045.0 1903.47  5055.0 1907.06
  5065.0 1911.10  5075.0 1914.56  5085.0 1917.10  5092.5 1919.33  5095.0 1919.33
#Mann=3,-1,0
  4883.2     0.1       0  4984.6    0.05       0  4988.6     0.1       0
Bank Sta=4984.6,4988.6
Exp/Cntr=0.3,0.1

Type RM Length L Ch R = 1,1856,454,454,454
BEGIN DESCRIPTION:
Stream0424 4.0
END DESCRIPTION:
XS GIS Cut Line= 3
      1870175.01     13962074.99      1870125.00     13962125.00
      1869975.01     13962324.98
#Sta/Elev= 30
  4924.2 1910.01  4927.7 1910.01  4938.4 1904.94  4952.5 1899.72  4980.8 1877.96
  4991.4 1871.23  4998.0 1871.23  5002.2 1870.27  5006.5 1868.42  5006.7 1867.92
  5010.2 1867.92  5010.5 1868.42  5031.4 1869.21  5037.6 1880.01  5052.2 1883.40
  5066.8 1885.51  5094.9 1888.23  5102.2 1890.28  5108.5 1890.66  5116.8 1892.51
  5123.0 1892.97  5131.4 1894.94  5137.6 1895.58  5152.2 1899.78  5173.0 1904.37
  5187.6 1906.35  5208.5 1912.61  5216.8 1914.47  5241.8 1919.05  5244.9 1919.05
#Mann=3,-1,0
  4924.2     0.1       0  5006.5    0.05       0  5010.5     0.1       0
Bank Sta=5006.5,5010.5
Exp/Cntr=0.3,0.1

Type RM Length L Ch R = 1,1402,422,422,422
BEGIN DESCRIPTION:
Stream0424 3.0
END DESCRIPTION:
XS GIS Cut Line= 3
      1869975.03     13961774.98      1869725.00     13961975.00
      1869624.98     13962125.03
#Sta/Elev= 30
  4679.3 1936.36  4715.4 1928.82  4750.6 1918.91  4779.4 1912.61  4835.4 1894.07
  4893.0 1878.16  4921.9 1872.32  4928.3 1872.53  4942.7 1869.58  4977.9 1867.64
  4996.3 1863.47  5002.5 1863.47  5007.0 1859.39  5013.0 1859.90  5022.0 1854.09
  5024.1 1854.01  5026.0 1853.94  5026.3 1853.44  5030.0 1853.94  5043.1 1856.77
  5064.1 1856.74  5071.6 1859.97  5079.1 1864.79  5088.1 1868.22  5100.1 1874.03
  5107.7 1880.02  5115.2 1895.90  5136.2 1904.85  5176.8 1916.81  5179.8 1916.81
#Mann=5,-1,0
  4679.3     0.1       0  5024.1    0.07       0  5026.0    0.05       0
  5030.0    0.07       0  5088.1     0.1       0
Bank Sta=5026,5030
Exp/Cntr=0.3,0.1

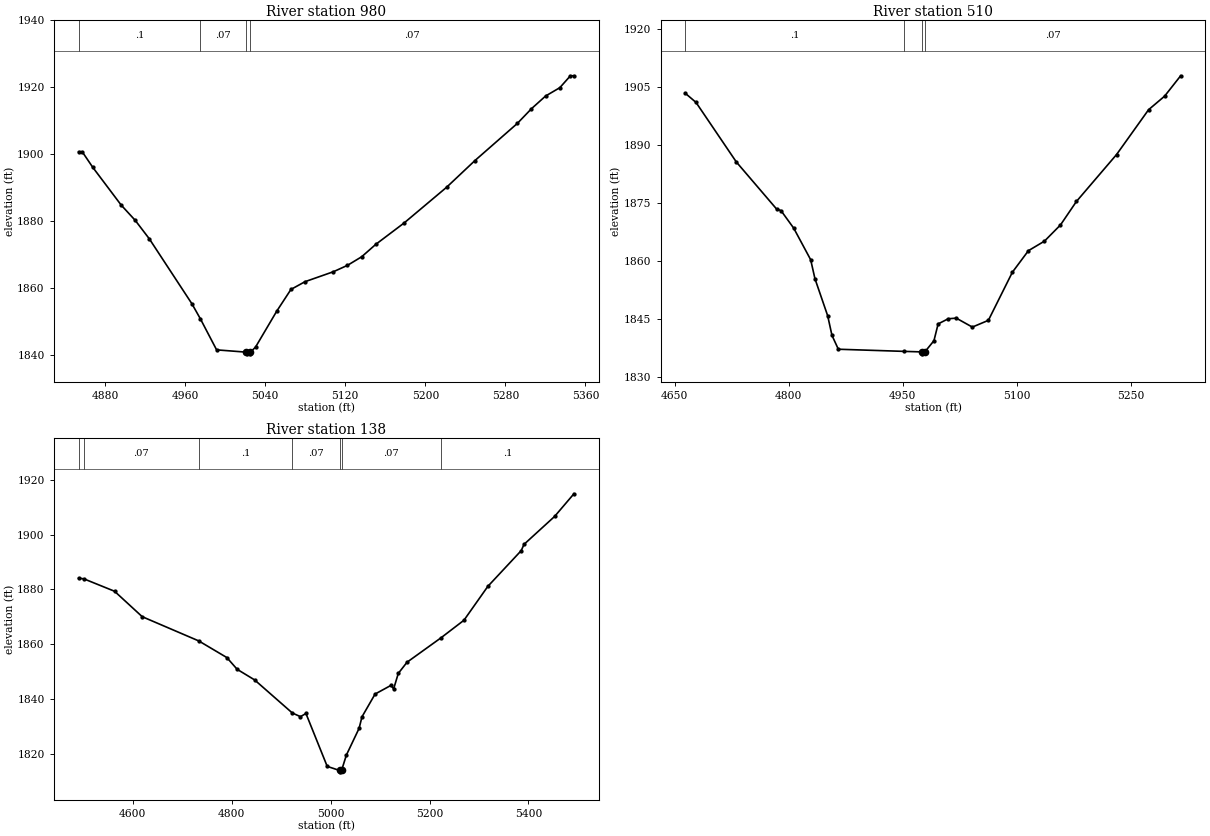
Type RM Length L Ch R = 1,980,470,470,470
BEGIN DESCRIPTION:
Stream0424 2.0
END DESCRIPTION:
XS GIS Cut Line= 3
      1869675.02     13961574.98      1869575.00     13961675.00
      1869325.00     13961925.00
#Sta/Elev= 30
  4853.5 1900.66  4857.1 1900.66  4867.7 1895.98  4896.0 1884.73  4910.1 1880.14
  4924.2 1874.61  4966.7 1855.22  4975.2 1850.70  4991.4 1841.43  5021.2 1840.74
  5021.5 1840.24  5025.0 1840.24  5025.2 1840.74  5030.3 1842.25  5051.5 1853.00
  5065.7 1859.50  5079.8 1861.82  5108.1 1864.79  5122.2 1866.70  5136.4 1869.27
  5150.5 1872.98  5178.8 1879.37  5221.2 1890.03  5249.5 1898.01  5291.9 1909.12
  5306.1 1913.54  5320.2 1917.33  5334.4 1919.82  5345.0 1923.38  5348.5 1923.38
#Mann=4,-1,0
  4853.5     0.1       0  4975.2    0.07       0  5021.2    0.05       0
  5025.2    0.07       0
Bank Sta=5021.2,5025.2
Exp/Cntr=0.3,0.1

Type RM Length L Ch R = 1,510,372,372,372
BEGIN DESCRIPTION:
Stream0424 1.0
END DESCRIPTION:
XS GIS Cut Line= 3
      1869525.02     13961274.99      1869225.00     13961425.00
      1869124.99     13961725.03
#Sta/Elev= 30
  4664.2 1903.26  4678.2 1900.92  4731.3 1885.50  4784.4 1873.30  4790.0 1872.94
  4806.8 1868.38  4829.1 1860.22  4834.7 1855.33  4851.5 1845.71  4857.1 1840.66
  4865.5 1837.07  4951.5 1836.52  4975.3 1836.38  4975.5 1835.88  4979.3 1836.38
  4991.3 1839.28  4996.8 1843.62  5010.2 1844.96  5020.7 1845.11  5041.8 1842.80
  5062.9 1844.54  5094.5 1856.99  5115.6 1862.56  5136.7 1865.03  5157.8 1869.22
  5178.8 1875.30  5231.5 1887.41  5273.7 1899.02  5294.8 1902.53  5315.9 1907.80
#Mann=4,-1,0
  4664.2     0.1       0  4951.5    0.07       0  4975.3    0.05       0
  4979.3    0.07       0
Bank Sta=4975.3,4979.3
Exp/Cntr=0.3,0.1

Type RM Length L Ch R = 1,138,0,0,0
BEGIN DESCRIPTION:
Stream0424 0.0
END DESCRIPTION:
XS GIS Cut Line= 4
      1869249.41     13960818.36      1868963.25     13961174.09
      1868896.29     13961385.31      1868946.69     13961704.63
#Sta/Elev= 30
  4490.5 1884.07  4501.0 1883.86  4563.1 1879.32  4619.1 1870.02  4733.3 1861.18
  4790.2 1855.09  4811.1 1850.79  4846.3 1846.93  4922.5 1834.85  4939.0 1833.50
  4950.1 1834.66  4993.1 1815.34  5018.1 1813.84  5018.3 1813.34  5022.1 1813.84
  5031.9 1819.48  5057.6 1829.25  5063.4 1833.44  5089.9 1841.76  5122.2 1844.95
  5127.4 1843.64  5136.8 1849.30  5154.5 1853.39  5222.9 1862.27  5269.6 1868.73
  5317.9 1881.11  5385.4 1894.17  5391.0 1896.45  5452.9 1906.66  5491.9 1914.93
#Mann=7,-1,0
  4490.5     0.1       0  4501.0    0.07       0  4733.3     0.1       0
  4922.5    0.07       0  5018.1    0.05       0  5022.1    0.07       0
  5222.9     0.1       0
Bank Sta=5018.1,5022.1
Exp/Cntr=0.3,0.1

Chan Stop Cuts=-1