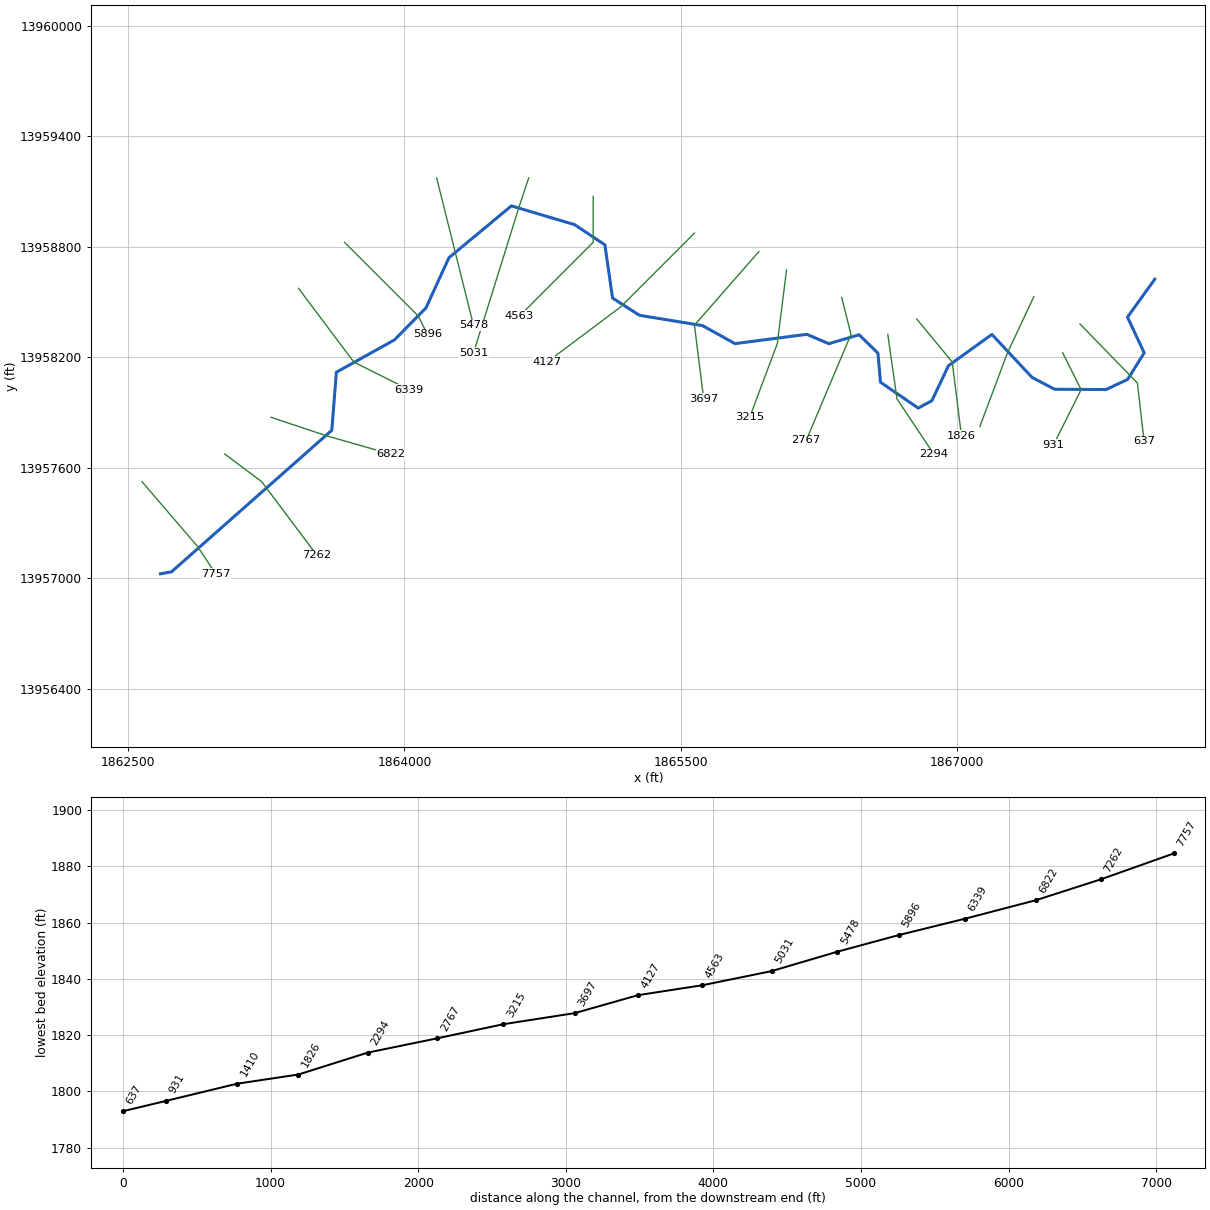
--- Stream0425.prj (project) ---

Proj Title=Stream0425 Base Level Engineering
Current Plan=p01
Default Exp/Contr=0.3,0.1
English Units
Geom File=g01
Flow File=f01
Plan File=p01
BEGIN DESCRIPTION:
Stream0425
END DESCRIPTION:

--- Stream0425.p01 (plan) ---

Plan Title=Multiple Run
Short Identifier=Multiple
Geom File=g01
Flow File=f01
Subcritical Flow
K Sum by GR= 0
Std Step Tol= 0.01
Critical Tol= 0.01
Num of Std Step Trials= 20
Max Error Tol= 0.3
Flow Tol Ratio= 0.001
Split Flow NTrial= 30
Split Flow Tol= 0.02
Split Flow Ratio= 0.02
Log Output Level= 0
Friction Slope Method= 1
Unsteady Friction Slope Method= 2
Unsteady Bridges Friction Slope Method= 1
Parabolic Critical Depth
Global Vel Dist=  1 , 1 , 1
Global Log Level= 0
CheckData=True
Encroach Param= -1, 0, 0, 0
BEGIN DESCRIPTION:
Multiple Run
END DESCRIPTION:

--- Stream0425.f01 (steady flow) ---

Flow Title=Multiple
Number of Profiles=7
Profile Names=10-year,25-year,50-year,1pct_min,100-year,1pct_plu,500-year
River Rch & RM= Stream0425,Reach-1,7757
    2400    4294    6179    4289    8557   17073   16227
River Rch & RM= Stream0425,Reach-1,2767
    2430    4342    6243    4328    8636   17230   16339
Boundary for River Rch & Prof#=Stream0425,Reach-1,1
Up Type=0
Dn Type=3
Dn Slope=0.005
Boundary for River Rch & Prof#=Stream0425,Reach-1,2
Up Type=0
Dn Type=3
Dn Slope=0.005
Boundary for River Rch & Prof#=Stream0425,Reach-1,3
Up Type=0
Dn Type=3
Dn Slope=0.005
Boundary for River Rch & Prof#=Stream0425,Reach-1,4
Up Type=0
Dn Type=3
Dn Slope=0.005
Boundary for River Rch & Prof#=Stream0425,Reach-1,5
Up Type=0
Dn Type=3
Dn Slope=0.005
Boundary for River Rch & Prof#=Stream0425,Reach-1,6
Up Type=0
Dn Type=3
Dn Slope=0.005
Boundary for River Rch & Prof#=Stream0425,Reach-1,7
Up Type=0
Dn Type=3
Dn Slope=0.005

--- Stream0425.g01 (geometry) ---

Geom Title=Existing Conditions

River Reach=Stream0425,Reach-1
Reach XY= 30
      1862675.00     13957025.00      1862734.79     13957035.51
      1863605.56     13957804.45      1863630.18     13958119.56
      1863945.09     13958294.78      1864116.86     13958468.94
      1864241.64     13958741.68      1864580.89     13959023.03
      1864923.50     13958921.38      1865088.63     13958811.54
      1865130.36     13958522.30      1865276.56     13958428.76
      1865619.07     13958372.75      1865795.03     13958275.06
      1866185.17     13958325.50      1866304.82     13958274.72
      1866469.12     13958323.04      1866571.46     13958223.54
      1866585.47     13958065.18      1866790.47     13957924.99
      1866864.37     13957964.88      1866954.61     13958155.16
      1867190.47     13958325.01      1867408.32     13958091.64
      1867530.93     13958027.24      1867809.79     13958025.51
      1867927.55     13958080.73      1868017.50     13958225.00
      1867926.79     13958418.89      1868075.00     13958625.00

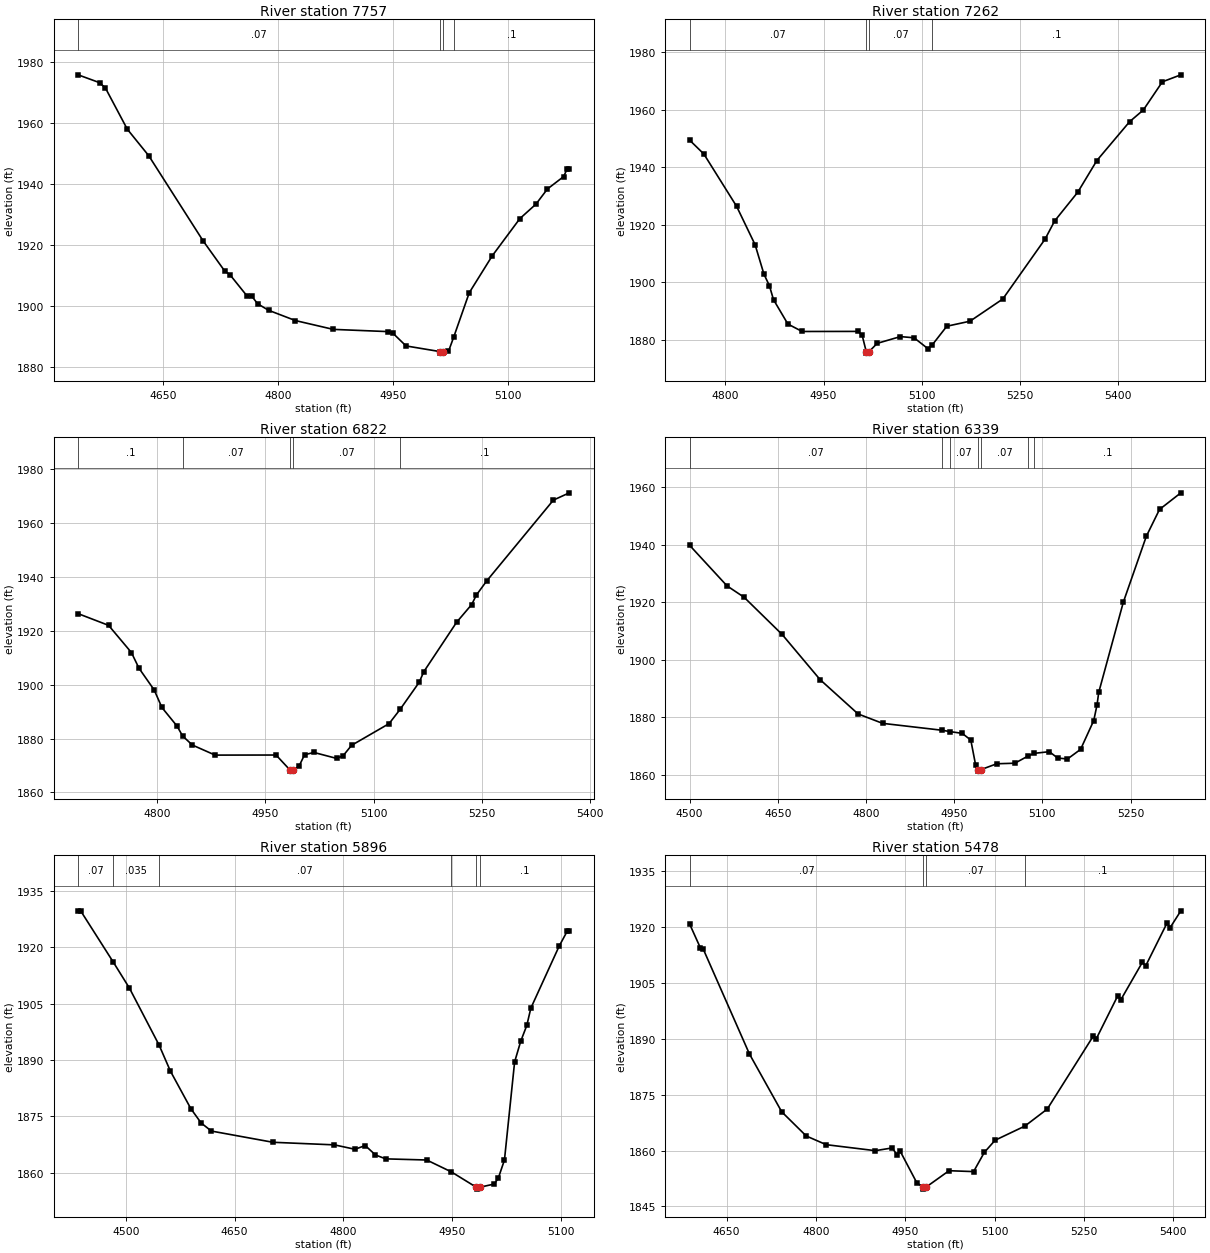
Type RM Length L Ch R = 1,7757,495,495,495
BEGIN DESCRIPTION:
Stream0425 16.0
END DESCRIPTION:
XS GIS Cut Line= 3
      1862574.99     13957525.01      1862875.00     13957175.00
      1862975.02     13957024.98
#Sta/Elev= 30
  4539.0 1975.83  4567.0 1973.26  4574.7 1971.49  4603.2 1958.00  4631.2 1949.30
  4702.0 1921.43  4730.5 1911.43  4737.1 1910.30  4759.1 1903.42  4765.7 1903.23
  4773.3 1900.74  4787.6 1898.60  4822.7 1895.22  4872.1 1892.33  4943.5 1891.60
  4950.1 1891.04  4967.1 1886.90  5011.5 1885.04  5011.7 1884.54  5015.6 1885.04
  5022.5 1885.11  5029.4 1889.85  5049.6 1904.34  5079.6 1916.45  5115.7 1928.67
  5136.7 1933.41  5151.7 1938.39  5172.8 1942.45  5177.3 1944.89  5180.3 1944.89
#Mann=4,-1,0
  4539.0    0.07       0  5011.5    0.05       0  5015.6    0.07       0
  5029.4     0.1       0
Bank Sta=5011.5,5015.6
Exp/Cntr=0.3,0.1

Type RM Length L Ch R = 1,7262,440,440,440
BEGIN DESCRIPTION:
Stream0425 15.0
END DESCRIPTION:
XS GIS Cut Line= 3
      1863025.02     13957674.98      1863225.00     13957525.00
      1863525.02     13957124.98
#Sta/Elev= 30
  4745.5 1949.44  4767.3 1944.60  4817.3 1926.39  4845.5 1913.04  4859.0 1902.81
  4867.3 1898.81  4873.6 1893.93  4895.5 1885.46  4917.3 1882.86  5002.8 1882.89
  5009.0 1881.48  5015.2 1875.83  5015.5 1875.33  5019.4 1875.83  5031.9 1878.73
  5067.3 1881.08  5088.2 1880.67  5109.0 1876.94  5115.4 1878.03  5138.2 1884.69
  5173.6 1886.44  5223.6 1894.15  5288.2 1915.00  5302.8 1921.31  5338.2 1931.35
  5367.3 1942.35  5417.3 1955.86  5438.2 1959.92  5467.3 1969.73  5495.5 1972.16
#Mann=4,-1,0
  4745.5    0.07       0  5015.2    0.05       0  5019.4    0.07       0
  5115.4     0.1       0
Bank Sta=5015.2,5019.4
Exp/Cntr=0.3,0.1

Type RM Length L Ch R = 1,6822,483,483,483
BEGIN DESCRIPTION:
Stream0425 14.0
END DESCRIPTION:
XS GIS Cut Line= 3
      1863275.00     13957875.00      1863575.00     13957775.00
      1863924.96     13957675.01
#Sta/Elev= 30
  4690.9 1926.40  4733.1 1922.05  4764.7 1911.96  4775.2 1906.13  4796.3 1898.04
  4806.9 1891.56  4827.9 1884.64  4835.6 1880.98  4849.0 1877.62  4880.6 1873.87
  4965.0 1873.90  4984.0 1868.42  4984.2 1867.92  4988.2 1868.42  4996.6 1869.64
  5004.5 1874.02  5017.5 1874.85  5048.7 1872.65  5057.8 1873.61  5069.5 1877.49
  5121.5 1885.56  5136.9 1890.90  5163.1 1900.88  5169.6 1904.85  5215.1 1923.24
  5235.9 1929.79  5242.4 1933.32  5256.7 1938.56  5349.0 1968.56  5371.1 1971.26
#Mann=5,-1,0
  4690.9     0.1       0  4835.6    0.07       0  4984.0    0.05       0
  4988.2    0.07       0  5136.9     0.1       0
Bank Sta=4984,4988.2
Exp/Cntr=0.3,0.1

Type RM Length L Ch R = 1,6339,443,443,443
BEGIN DESCRIPTION:
Stream0425 13.0
END DESCRIPTION:
XS GIS Cut Line= 3
      1863424.98     13958575.02      1863725.00     13958175.00
      1864024.97     13958025.02
#Sta/Elev= 30
  4500.0 1939.82  4563.6 1925.72  4592.7 1921.75  4657.3 1908.83  4721.9 1893.12
  4786.5 1881.19  4828.2 1877.92  4929.7 1875.51  4943.6 1875.03  4963.6 1874.44
  4978.2 1872.11  4986.5 1863.32  4990.4 1861.81  4990.7 1861.31  4995.1 1861.81
  5022.4 1863.87  5053.1 1864.06  5075.3 1866.53  5085.5 1867.48  5111.8 1868.07
  5125.8 1865.87  5142.6 1865.53  5164.9 1868.88  5187.3 1878.91  5192.9 1884.38
  5195.7 1888.65  5237.6 1920.06  5276.7 1942.96  5299.1 1952.28  5335.4 1958.06
#Mann=7,-1,0
  4500.0    0.07       0  4929.7   0.035       0  4943.6    0.07       0
  4990.4    0.05       0  4995.1    0.07       0  5075.3   0.035       0
  5085.5     0.1       0
Bank Sta=4990.4,4995.1
Exp/Cntr=0.3,0.1

Type RM Length L Ch R = 1,5896,418,418,418
BEGIN DESCRIPTION:
Stream0425 12.0
END DESCRIPTION:
XS GIS Cut Line= 3
      1863675.02     13958824.98      1864075.00     13958425.00
      1864125.02     13958324.97
#Sta/Elev= 30
  4434.1 1929.72  4437.6 1929.72  4482.8 1916.00  4504.8 1909.16  4545.8 1893.95
  4561.4 1887.02  4589.6 1877.01  4603.8 1873.20  4617.9 1871.05  4702.8 1868.06
  4787.6 1867.37  4815.9 1866.20  4830.1 1867.19  4844.2 1864.68  4858.3 1863.64
  4914.9 1863.34  4948.8 1860.18  4983.3 1856.08  4983.6 1855.58  4988.0 1856.08
  5008.1 1856.94  5013.7 1858.56  5022.1 1863.35  5036.1 1889.46  5044.5 1894.96
  5052.9 1899.19  5058.5 1903.80  5097.6 1920.34  5108.8 1924.35  5111.6 1924.35
#Mann=6,-1,0
  4434.1    0.07       0  4482.8   0.035       0  4545.8    0.07       0
  4948.8     0.1       0  4983.3    0.05       0  4988.0     0.1       0
Bank Sta=4983.3,4988
Exp/Cntr=0.3,0.1

Type RM Length L Ch R = 1,5478,447,447,447
BEGIN DESCRIPTION:
Stream0425 11.0
END DESCRIPTION:
XS GIS Cut Line= 3
      1864175.01     13959174.95      1864275.00     13958775.00
      1864375.01     13958374.97
#Sta/Elev= 30
  4588.0 1920.76  4606.0 1914.38  4611.1 1913.95  4688.5 1885.87  4742.6 1870.39
  4783.8 1863.90  4817.3 1861.57  4899.8 1859.96  4928.1 1860.70  4935.8 1858.93
  4941.0 1859.97  4969.3 1851.38  4979.9 1850.15  4980.2 1849.65  4984.6 1850.15
  5023.5 1854.59  5064.7 1854.35  5082.7 1859.50  5100.8 1862.76  5150.7 1866.55
  5188.4 1871.13  5265.7 1890.72  5270.8 1890.02  5306.9 1901.57  5312.1 1900.50
  5348.1 1910.51  5353.3 1909.43  5389.4 1921.01  5394.5 1919.75  5412.6 1924.28
#Mann=4,-1,0
  4588.0    0.07       0  4979.9    0.05       0  4984.6    0.07       0
  5150.7     0.1       0
Bank Sta=4979.9,4984.6
Exp/Cntr=0.3,0.1

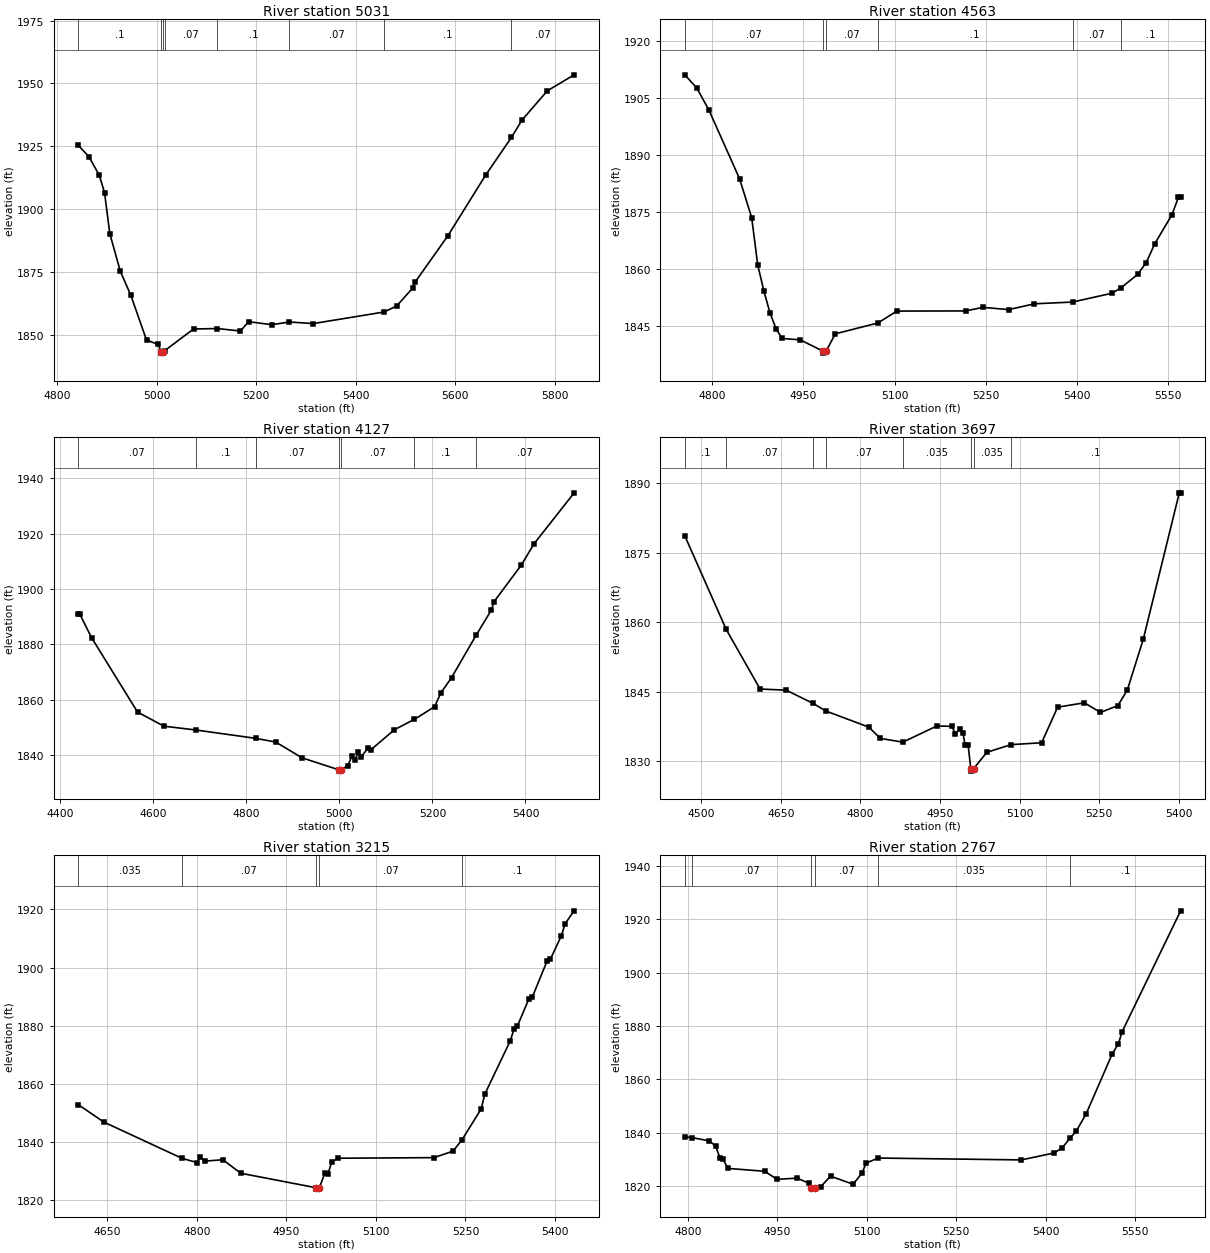
Type RM Length L Ch R = 1,5031,468,468,468
BEGIN DESCRIPTION:
Stream0425 10.0
END DESCRIPTION:
XS GIS Cut Line= 3
      1864674.99     13959174.98      1864625.00     13959025.00
      1864375.01     13958225.05
#Sta/Elev= 30
  4842.8 1925.36  4863.9 1920.93  4884.9 1913.48  4895.5 1906.52  4906.0 1890.32
  4927.1 1875.33  4948.2 1865.77  4979.8 1847.95  5003.5 1846.18  5008.9 1843.24
  5009.3 1842.74  5013.8 1843.24  5016.4 1843.73  5074.2 1852.33  5122.1 1852.52
  5168.5 1851.53  5184.8 1855.25  5231.4 1854.04  5266.8 1855.12  5314.7 1854.49
  5456.8 1859.09  5482.3 1861.46  5514.3 1868.57  5520.0 1871.16  5585.0 1889.32
  5660.9 1913.46  5713.0 1928.54  5734.3 1935.46  5785.1 1947.07  5839.0 1953.43
#Mann=8,-1,0
  4842.8     0.1       0  5008.9    0.05       0  5013.8     0.1       0
  5016.4    0.07       0  5122.1     0.1       0  5266.8    0.07       0
  5456.8     0.1       0  5713.0    0.07       0
Bank Sta=5008.9,5013.8
Exp/Cntr=0.3,0.1

Type RM Length L Ch R = 1,4563,436,436,436
BEGIN DESCRIPTION:
Stream0425 9.0
END DESCRIPTION:
XS GIS Cut Line= 3
      1865025.00     13959075.00      1865025.00     13958825.00
      1864624.99     13958424.99
#Sta/Elev= 30
  4754.8 1911.13  4774.8 1907.59  4794.8 1901.73  4844.8 1883.75  4864.8 1873.49
  4874.8 1860.97  4884.8 1854.18  4894.8 1848.42  4904.8 1844.18  4914.8 1841.60
  4944.8 1841.23  4982.4 1838.23  4982.7 1837.73  4987.3 1838.23  5002.3 1842.82
  5072.4 1845.68  5103.8 1848.82  5216.9 1848.86  5245.2 1849.80  5287.6 1849.21
  5330.1 1850.74  5392.7 1851.20  5457.4 1853.52  5472.4 1854.95  5499.8 1858.50
  5513.9 1861.60  5528.1 1866.62  5556.3 1874.25  5567.0 1878.90  5570.5 1878.90
#Mann=6,-1,0
  4754.8    0.07       0  4982.4    0.05       0  4987.3    0.07       0
  5072.4     0.1       0  5392.7    0.07       0  5472.4     0.1       0
Bank Sta=4982.4,4987.3
Exp/Cntr=0.3,0.1

Type RM Length L Ch R = 1,4127,430,430,430
BEGIN DESCRIPTION:
Stream0425 8.0
END DESCRIPTION:
XS GIS Cut Line= 3
      1865575.00     13958875.00      1865175.00     13958475.00
      1864774.99     13958174.99
#Sta/Elev= 30
  4438.9 1890.83  4442.4 1890.83  4467.2 1882.49  4566.2 1855.55  4622.7 1850.46
  4692.0 1849.07  4819.7 1846.07  4863.2 1844.72  4919.7 1839.02  4998.5 1834.71
  4998.9 1834.21  5003.6 1834.71  5018.1 1836.11  5026.5 1839.52  5032.7 1838.12
  5041.0 1841.04  5047.3 1839.47  5061.9 1842.62  5068.1 1841.98  5118.1 1849.16
  5161.4 1852.94  5204.6 1857.50  5218.1 1862.47  5241.0 1867.99  5293.7 1883.28
  5326.5 1892.40  5332.7 1895.52  5391.0 1908.68  5418.1 1916.32  5504.6 1934.80
#Mann=7,-1,0
  4438.9    0.07       0  4692.0     0.1       0  4819.7    0.07       0
  4998.5    0.05       0  5003.6    0.07       0  5161.4     0.1       0
  5293.7    0.07       0
Bank Sta=4998.5,5003.6
Exp/Cntr=0.3,0.1

Type RM Length L Ch R = 1,3697,482,482,482
BEGIN DESCRIPTION:
Stream0425 7.0
END DESCRIPTION:
XS GIS Cut Line= 3
      1865925.01     13958775.01      1865575.00     13958375.00
      1865625.00     13957975.04
#Sta/Elev= 30
  4468.9 1878.62  4547.0 1858.40  4610.8 1845.55  4660.2 1845.29  4710.7 1842.44
  4734.5 1840.81  4815.8 1837.32  4837.6 1834.88  4879.8 1834.08  4944.0 1837.56
  4972.4 1837.49  4979.1 1835.81  4986.7 1836.87  4993.3 1836.06  4997.1 1833.50
  5002.9 1833.50  5008.0 1828.32  5008.4 1827.82  5013.1 1828.32  5038.2 1831.88
  5083.9 1833.54  5141.5 1833.94  5171.7 1841.63  5222.1 1842.57  5252.4 1840.49
  5285.1 1841.96  5302.8 1845.26  5333.0 1856.25  5401.0 1887.90  5403.5 1887.90
#Mann=8,-1,0
  4468.9     0.1       0  4547.0    0.07       0  4710.7   0.035       0
  4734.5    0.07       0  4879.8   0.035       0  5008.0   0.035       0
  5013.1   0.035       0  5083.9     0.1       0
Bank Sta=5008,5013.1
Exp/Cntr=0.3,0.1

Type RM Length L Ch R = 1,3215,448,448,448
BEGIN DESCRIPTION:
Stream0425 6.0
END DESCRIPTION:
XS GIS Cut Line= 3
      1866075.00     13958675.00      1866025.00     13958275.00
      1865875.01     13957875.01
#Sta/Elev= 30
  4601.8 1852.92  4644.6 1846.92  4776.1 1834.42  4800.8 1833.03  4805.9 1834.97
  4813.4 1833.52  4843.7 1833.99  4873.9 1829.35  4999.3 1824.40  4999.8 1823.90
  5005.4 1824.40  5014.7 1829.41  5020.0 1829.25  5026.3 1833.31  5037.0 1834.51
  5197.2 1834.72  5229.2 1836.94  5243.9 1840.71  5276.4 1851.46  5282.6 1856.58
  5325.3 1874.92  5331.5 1878.98  5336.9 1879.86  5356.5 1889.33  5361.8 1889.75
  5386.7 1902.23  5392.1 1902.78  5410.8 1911.00  5417.0 1915.10  5432.1 1919.49
#Mann=5,-1,0
  4601.8   0.035       0  4776.1    0.07       0  4999.3    0.05       0
  5005.4    0.07       0  5243.9     0.1       0
Bank Sta=4999.3,5005.4
Exp/Cntr=0.3,0.1

Type RM Length L Ch R = 1,2767,473,473,473
BEGIN DESCRIPTION:
Stream0425 5.0
END DESCRIPTION:
XS GIS Cut Line= 3
      1866375.00     13958525.01      1866425.00     13958325.00
      1866181.74     13957749.04
#Sta/Elev= 30
  4794.7 1838.52  4806.1 1838.22  4835.9 1836.98  4846.3 1835.05  4854.0 1830.40
  4859.1 1830.01  4866.9 1826.66  4928.7 1825.58  4949.3 1822.57  4982.8 1823.01
  5003.6 1821.07  5007.0 1819.39  5007.5 1818.89  5013.1 1819.39  5022.6 1819.79
  5039.1 1823.74  5076.9 1820.73  5092.0 1824.95  5098.6 1828.64  5119.1 1830.54
  5359.1 1829.84  5413.4 1832.42  5427.3 1834.26  5440.6 1838.00  5451.0 1840.59
  5467.7 1847.11  5511.1 1869.41  5521.9 1873.40  5527.6 1877.69  5626.1 1923.20
#Mann=6,-1,0
  4794.7   0.035       0  4806.1    0.07       0  5007.0    0.05       0
  5013.1    0.07       0  5119.1   0.035       0  5440.6     0.1       0
Bank Sta=5007,5013.1
Exp/Cntr=0.3,0.1

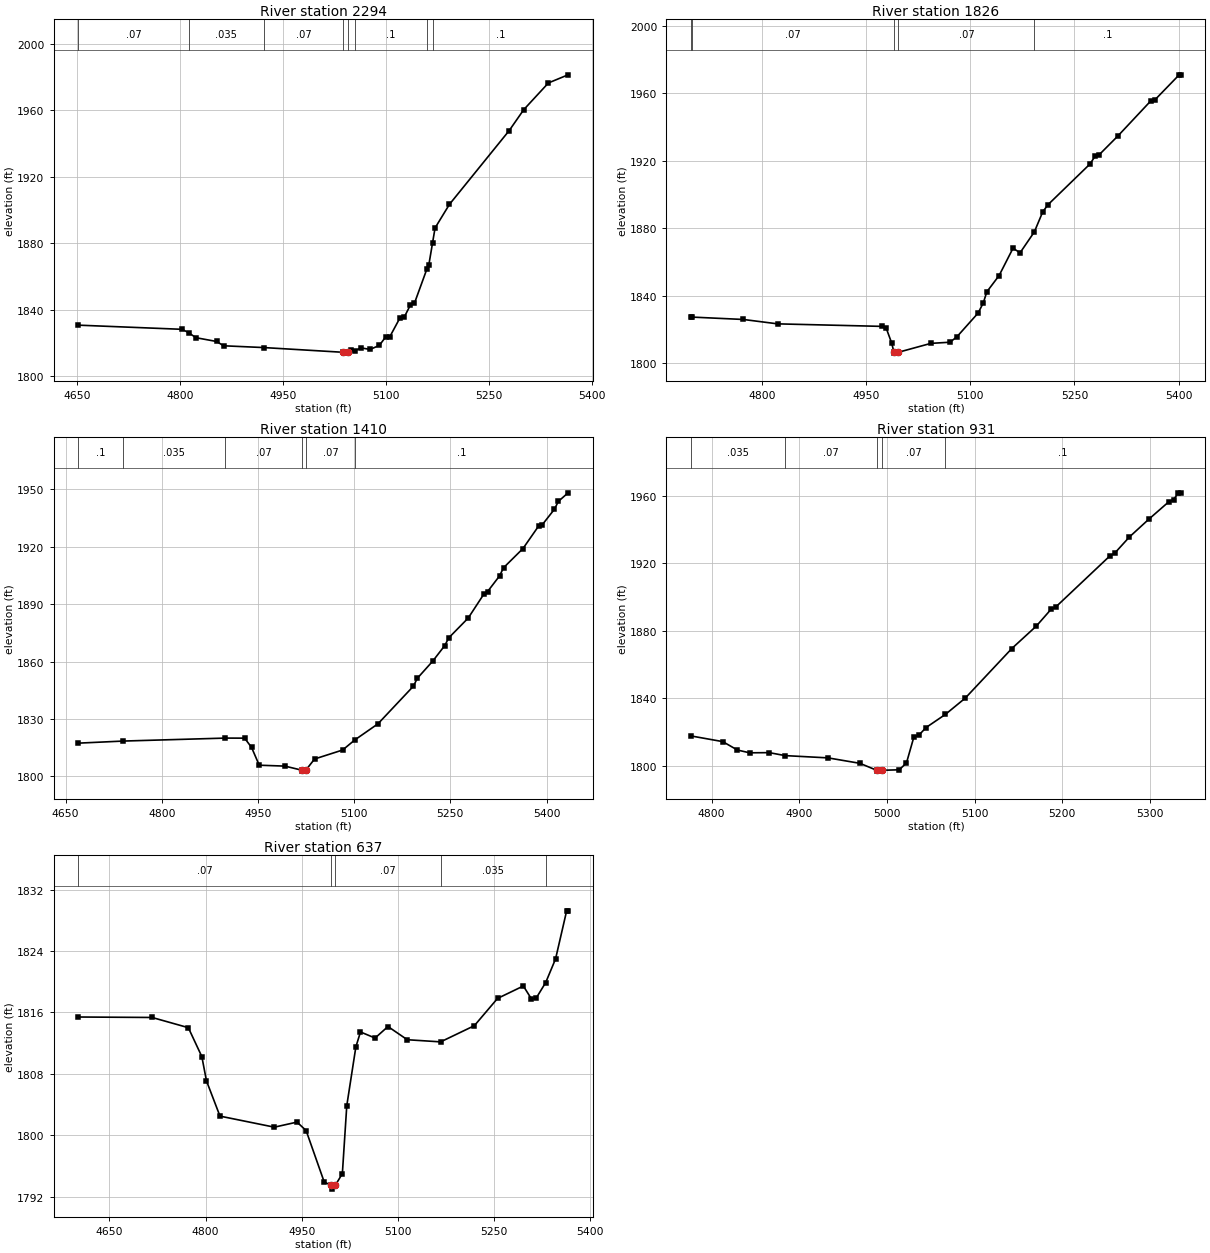
Type RM Length L Ch R = 1,2294,468,468,468
BEGIN DESCRIPTION:
Stream0425 4.0
END DESCRIPTION:
XS GIS Cut Line= 3
      1866625.01     13958324.96      1866675.00     13957975.00
      1866875.02     13957674.97
#Sta/Elev= 30
  4651.6 1830.63  4803.1 1828.12  4812.7 1826.14  4823.3 1823.08  4853.6 1820.79
  4863.7 1818.21  4922.7 1817.13  5038.1 1814.29  5038.6 1813.79  5044.3 1814.29
  5048.7 1815.79  5055.4 1815.22  5063.7 1816.97  5077.2 1816.02  5090.7 1818.44
  5099.8 1823.48  5105.8 1823.54  5120.8 1835.05  5126.8 1835.34  5135.8 1842.60
  5141.8 1843.76  5160.2 1864.66  5162.9 1867.11  5168.3 1880.32  5171.9 1889.13
  5192.9 1903.35  5280.0 1947.76  5301.1 1960.29  5337.1 1976.39  5365.7 1981.27
#Mann=8,-1,0
  4651.6    0.07       0  4812.7   0.035       0  4922.7    0.07       0
  5038.1    0.05       0  5044.3    0.07       0  5055.4     0.1       0
  5160.2    0.07       0  5168.3     0.1       0
Bank Sta=5038.1,5044.3
Exp/Cntr=0.3,0.1

Type RM Length L Ch R = 1,1826,416,416,416
BEGIN DESCRIPTION:
Stream0425 3.0
END DESCRIPTION:
XS GIS Cut Line= 3
      1866782.28     13958408.76      1866975.00     13958175.00
      1867025.00     13957774.98
#Sta/Elev= 30
  4697.3 1827.38  4698.4 1827.38  4772.9 1825.96  4822.4 1823.36  4972.3 1821.87
  4978.8 1820.75  4986.6 1812.02  4989.9 1806.53  4990.4 1806.03  4996.2 1806.53
  5043.1 1811.81  5070.8 1812.49  5080.9 1815.84  5111.1 1829.73  5118.7 1835.84
  5123.7 1842.33  5141.4 1851.96  5161.5 1868.18  5171.6 1865.43  5192.2 1877.83
  5204.3 1889.70  5211.9 1893.94  5272.4 1918.04  5279.9 1922.75  5285.0 1923.25
  5312.7 1934.67  5360.5 1955.62  5365.6 1955.87  5400.9 1970.83  5403.4 1970.83
#Mann=5,-1,0
  4697.3   0.035       0  4698.4    0.07       0  4989.9    0.05       0
  4996.2    0.07       0  5192.2     0.1       0
Bank Sta=4989.9,4996.2
Exp/Cntr=0.3,0.1

Type RM Length L Ch R = 1,1410,479,479,479
BEGIN DESCRIPTION:
Stream0425 2.0
END DESCRIPTION:
XS GIS Cut Line= 3
      1867418.07     13958529.90      1867275.00     13958225.00
      1867125.00     13957825.00
#Sta/Elev= 30
  4669.5 1817.37  4739.6 1818.46  4899.3 1820.02  4929.2 1819.99  4940.0 1815.17
  4952.0 1805.85  4992.1 1805.38  5018.3 1803.26  5018.8 1802.76  5024.6 1803.26
  5038.3 1809.10  5082.0 1813.79  5101.2 1819.10  5137.1 1827.47  5192.3 1847.11
  5198.5 1851.26  5222.6 1860.26  5241.3 1868.37  5247.5 1872.39  5277.8 1882.72
  5302.7 1895.48  5308.0 1896.56  5326.7 1904.74  5332.9 1909.00  5363.2 1919.03
  5388.1 1931.03  5393.5 1931.56  5412.1 1939.50  5418.4 1943.67  5433.5 1948.14
#Mann=6,-1,0
  4669.5     0.1       0  4739.6   0.035       0  4899.3    0.07       0
  5018.3    0.05       0  5024.6    0.07       0  5101.2     0.1       0
Bank Sta=5018.3,5024.6
Exp/Cntr=0.3,0.1

Type RM Length L Ch R = 1,931,294,294,294
BEGIN DESCRIPTION:
Stream0425 1.0
END DESCRIPTION:
XS GIS Cut Line= 3
      1867575.01     13958224.97      1867675.00     13958025.00
      1867524.99     13957724.99
#Sta/Elev= 30
  4776.4 1817.56  4812.7 1814.19  4829.5 1809.19  4843.4 1807.55  4865.8 1807.65
  4883.9 1805.89  4932.9 1804.54  4969.2 1801.32  4988.4 1797.19  4988.9 1796.69
  4994.7 1797.19  5014.0 1797.48  5022.3 1801.51  5030.7 1816.82  5036.3 1817.93
  5044.7 1822.54  5066.7 1830.31  5089.4 1839.99  5142.5 1869.38  5170.5 1882.71
  5187.2 1892.60  5192.8 1894.09  5254.3 1924.25  5259.9 1925.94  5276.7 1935.54
  5299.0 1946.15  5321.4 1956.30  5327.0 1957.67  5332.6 1961.69  5335.4 1961.69
#Mann=5,-1,0
  4776.4   0.035       0  4883.9    0.07       0  4988.4    0.05       0
  4994.7    0.07       0  5066.7     0.1       0
Bank Sta=4988.4,4994.7
Exp/Cntr=0.3,0.1

Type RM Length L Ch R = 1,637,0,0,0
BEGIN DESCRIPTION:
Stream0425 0.0
END DESCRIPTION:
XS GIS Cut Line= 3
      1867668.56     13958382.00      1867980.55     13958061.08
      1868016.83     13957745.64
#Sta/Elev= 30
  4600.9 1815.41  4716.5 1815.35  4773.1 1814.02  4794.2 1810.25  4801.4 1807.10
  4822.5 1802.50  4907.4 1801.06  4942.8 1801.72  4957.0 1800.62  4985.3 1793.91
  4996.3 1793.49  4996.8 1792.99  5002.6 1793.49  5013.6 1795.01  5020.5 1803.86
  5034.7 1811.52  5041.9 1813.46  5064.7 1812.67  5084.8 1814.17  5115.0 1812.45
  5167.0 1812.17  5219.7 1814.28  5255.9 1817.83  5296.2 1819.45  5308.8 1817.77
  5316.3 1817.88  5331.1 1819.90  5346.5 1822.98  5363.8 1829.24  5366.0 1829.24
#Mann=5,-1,0
  4600.9    0.07       0  4996.3    0.05       0  5002.6    0.07       0
  5167.0   0.035       0  5331.1     0.1       0
Bank Sta=4996.3,5002.6
Exp/Cntr=0.3,0.1

Chan Stop Cuts=-1