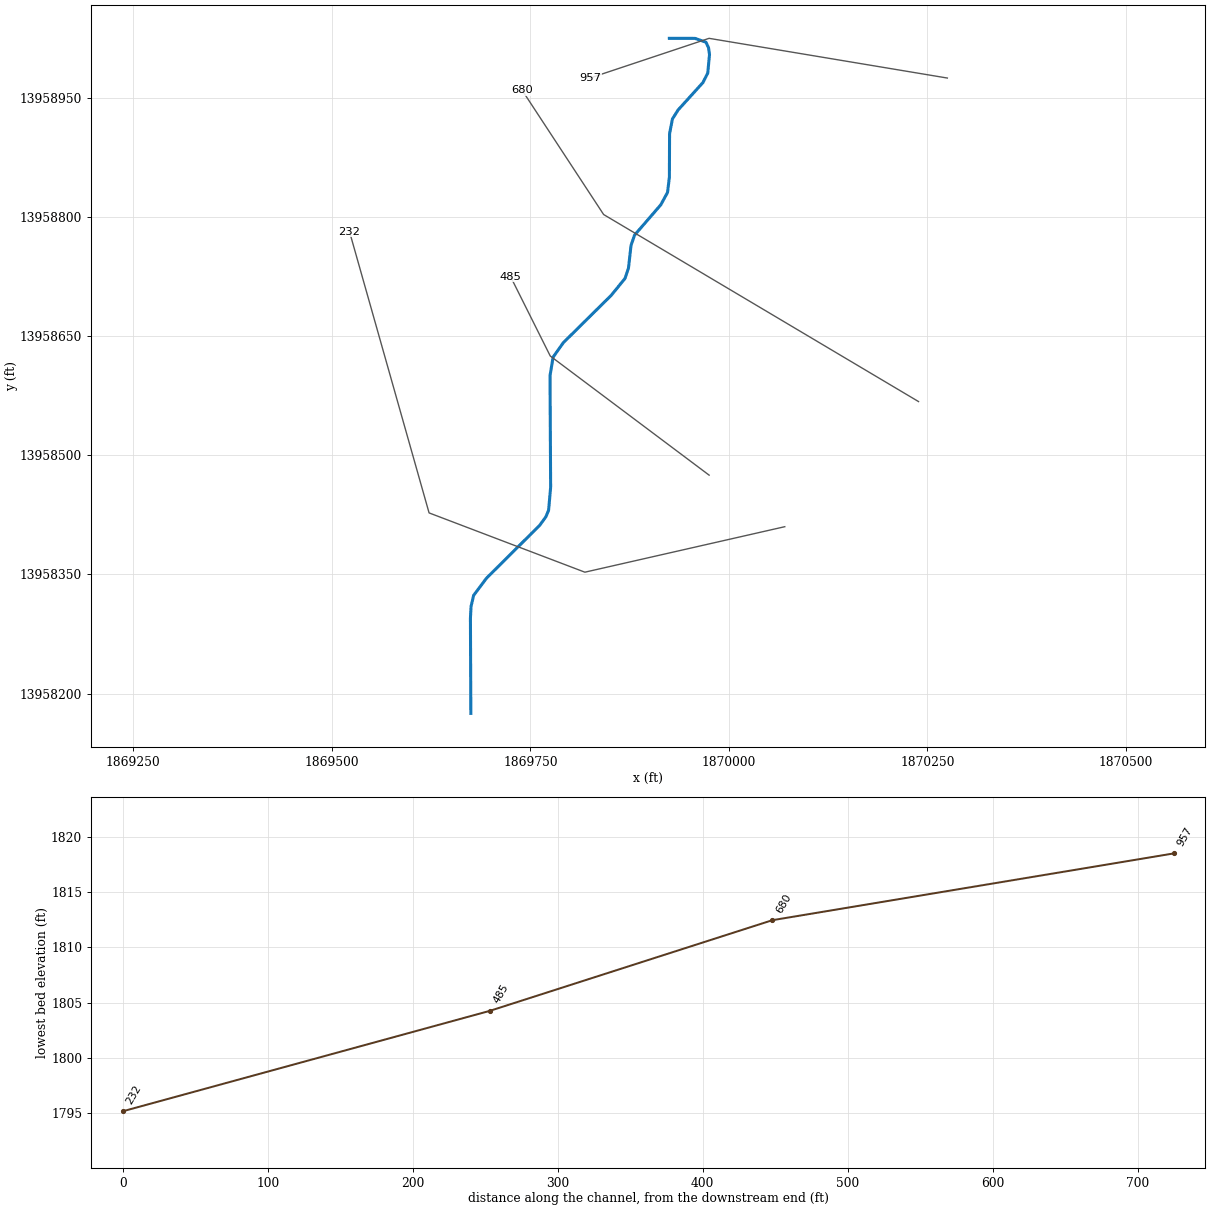
--- Stream0426.prj (project) ---

Proj Title=Stream0426 Base Level Engineering
Current Plan=p01
Default Exp/Contr=0.3,0.1
English Units
Geom File=g01
Flow File=f01
Plan File=p01
Y Axis Title=Elevation
X Axis Title(PF)=Main Channel Distance
X Axis Title(XS)=Station
BEGIN DESCRIPTION:
Stream0426
END DESCRIPTION:
DSS Export Rating Curves= 0
DSS Export Rating Curve Sorted= 0
DSS Export Volume Flow Curves= 0
DXF OffsetX= 0
DXF OffsetY= 0
DXF ScaleX= 1
DXF ScaleY= 10

--- Stream0426.p01 (plan) ---

Plan Title=Multiple Run
Short Identifier=Multiple
Geom File=g01
Flow File=f01
Subcritical Flow
K Sum by GR= 0
Std Step Tol= 0.01
Critical Tol= 0.01
Num of Std Step Trials= 20
Max Error Tol= 0.3
Flow Tol Ratio= 0.001
Split Flow NTrial= 30
Split Flow Tol= 0.02
Split Flow Ratio= 0.02
Log Output Level= 0
Friction Slope Method= 1
Unsteady Friction Slope Method= 2
Unsteady Bridges Friction Slope Method= 1
Parabolic Critical Depth
Global Vel Dist=  1 , 1 , 1
Global Log Level= 0
CheckData=True
Encroach Param= -1, 0, 0, 0
BEGIN DESCRIPTION:
Multiple Run
END DESCRIPTION:

--- Stream0426.f01 (steady flow) ---

Flow Title=Multiple
Number of Profiles=7
Profile Names=10-year,25-year,50-year,1pct_min,100-year,1pct_plu,500-year
River Rch & RM= Stream0426,Reach-1,957
     459     744    1003     658    1313    2619    2210
Boundary for River Rch & Prof#=Stream0426,Reach-1,1
Up Type=0
Dn Type=3
Dn Slope=0.005
Boundary for River Rch & Prof#=Stream0426,Reach-1,2
Up Type=0
Dn Type=3
Dn Slope=0.005
Boundary for River Rch & Prof#=Stream0426,Reach-1,3
Up Type=0
Dn Type=3
Dn Slope=0.005
Boundary for River Rch & Prof#=Stream0426,Reach-1,4
Up Type=0
Dn Type=3
Dn Slope=0.005
Boundary for River Rch & Prof#=Stream0426,Reach-1,5
Up Type=0
Dn Type=3
Dn Slope=0.005
Boundary for River Rch & Prof#=Stream0426,Reach-1,6
Up Type=0
Dn Type=3
Dn Slope=0.005
Boundary for River Rch & Prof#=Stream0426,Reach-1,7
Up Type=0
Dn Type=3
Dn Slope=0.005

--- Stream0426.g01 (geometry) ---

Geom Title=Existing Conditions
Program Version=4.10

River Reach=Stream0426      ,Reach-1
Reach XY= 30
        1869925.       13959025.      1869957.35     13959024.94
      1869971.02      13959020.1      1869974.29     13959013.27
      1869975.53     13959004.63      1869973.34     13958981.31
      1869967.22     13958969.26       1869935.9     13958934.71
      1869928.86     13958923.45      1869925.25     13958904.92
      1869925.01       13958850.      1869922.67     13958830.97
      1869914.17     13958815.35      1869881.14     13958777.17
      1869876.72     13958764.29      1869873.49     13958735.62
      1869869.15     13958722.71      1869851.94     13958701.55
      1869791.46     13958641.75      1869778.55     13958623.53
      1869774.71     13958600.12      1869775.49      13958459.8
      1869772.93     13958430.86      1869769.52     13958422.55
       1869761.6     13958411.69      1869694.65     13958345.15
      1869678.51     13958323.55      1869675.32     13958309.87
      1869674.49     13958295.21        1869675.       13958175.

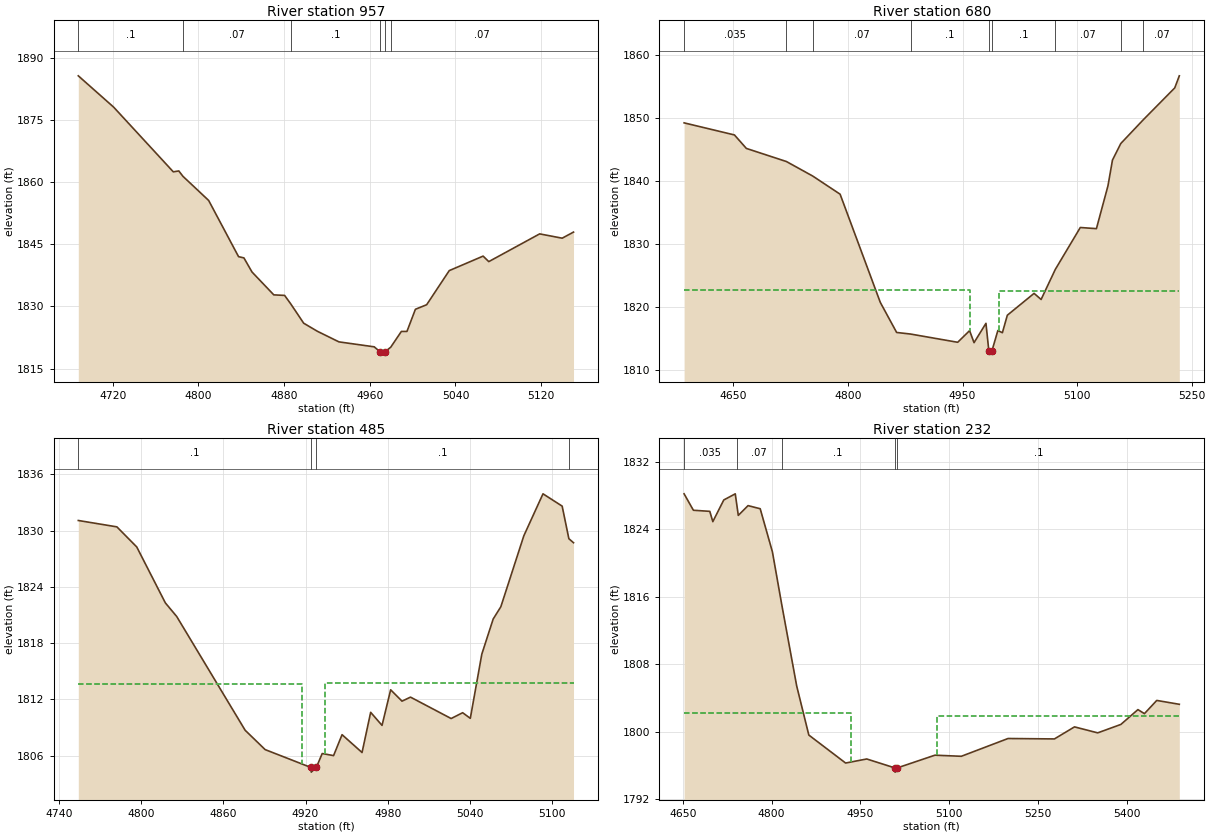
Type RM Length L Ch R = 1 ,957     ,277,277,277
BEGIN DESCRIPTION:
Stream0426 2.0
END DESCRIPTION:
XS GIS Cut Line= 3
      1870275.02       13958975.        1869975.       13959025.
      1869824.97     13958974.99
#Sta/Elev= 30
  4687.9 1885.69  4720.9 1878.13  4776.6  1862.5  4781.7 1862.72  4785.6 1861.42
  4809.6 1855.59  4837.5 1842.02  4842.5 1841.72  4850.1  1838.3  4870.4 1832.79
  4880.5 1832.66  4886.1 1830.66  4898.3 1825.95    4911 1824.01  4931.2 1821.44
  4964.2 1820.24  4969.8 1818.98    4970 1818.48  4973.8 1818.98  4979.5 1820.13
  4989.5 1823.96  4994.7 1823.96  5002.6 1829.31  5013.1 1830.41  5034.2 1838.65
  5065.8 1842.15  5071.1 1840.82  5118.6 1847.52  5139.6 1846.48  5150.2 1847.95
#Mann= 6 ,-1 , 0
  4687.9      .1       0  4785.6     .07       0  4886.1      .1       0
  4969.8     .05       0  4973.8      .1       0  4979.5     .07       0
Bank Sta=4969.8,4973.8
XS Rating Curve= 0 ,0
Exp/Cntr=0.3,0.1

Type RM Length L Ch R = 1 ,680     ,195,195,195
BEGIN DESCRIPTION:
Mapping XS d78c22a4
END DESCRIPTION:
XS GIS Cut Line= 3
      1870238.73     13958567.62      1869842.21     13958803.15
      1869739.68     13958959.54
#Sta/Elev= 30
  4585.6 1849.18  4651.5 1847.26  4667.1 1845.12  4719.5 1843.04    4754 1840.73
  4789.8 1837.85  4842.4 1820.67  4863.8 1815.89    4882 1815.64  4943.7 1814.33
  4959.3 1816.18  4965.1 1814.27  4980.7 1817.34  4984.5 1812.95  4984.8 1812.45
  4988.5 1812.95  4996.3  1816.2  5002.2 1815.85  5008.7 1818.63  5043.7  1822.1
  5052.9 1821.13  5071.5 1825.91  5104.2 1832.56  5125.3 1832.38  5140.4 1839.18
  5146.3 1843.27  5157.2  1845.9  5186.7 1849.68  5227.8 1854.73  5233.8 1856.65
#Mann= 9 ,-1 , 0
  4585.6    .035       0  4719.5      .1       0    4754     .07       0
    4882      .1       0  4984.5     .05       0  4988.5      .1       0
  5071.5     .07       0  5157.2      .1       0  5186.7     .07       0
#XS Ineff= 2 , 0
         4959.35  1822.7 4997.55         1822.46
Permanent Ineff=
       F       F
Bank Sta=4984.5,4988.5
XS Rating Curve= 0 ,0
Exp/Cntr=0.3,0.1

Type RM Length L Ch R = 1 ,485     ,253,253,253
BEGIN DESCRIPTION:
Stream0426 1.0
END DESCRIPTION:
XS GIS Cut Line= 3
      1869975.03     13958474.98        1869775.       13958625.
      1869725.02     13958724.97
#Sta/Elev= 30
    4754 1831.07  4782.2 1830.39  4796.7 1828.25  4817.6 1822.29  4825.9 1820.84
  4875.9 1808.72  4890.5 1806.66  4923.9 1804.76  4924.2 1804.26  4927.9 1804.76
  4932.2 1806.24  4940.5 1806.02  4946.7 1808.25  4961.3 1806.35  4967.6 1810.63
  4975.9 1809.24  4982.2 1813.03  4990.5 1811.82  4996.7 1812.25  5026.4 1809.97
  5034.8 1810.59  5040.4 1809.99  5048.8 1816.83  5057.1 1820.57  5062.7 1821.88
  5079.5 1829.44  5093.5 1833.91  5107.5  1832.6  5112.4 1829.13  5115.8  1828.7
#Mann= 4 ,-1 , 0
    4754      .1       0  4923.9     .05       0  4927.9      .1       0
  5112.4    .063       0
#XS Ineff= 2 , 0
         4917.23 1813.68 4934.26         1813.79
Permanent Ineff=
       F       F
Bank Sta=4923.9,4927.9
XS Rating Curve= 0 ,0
Exp/Cntr=0.3,0.1

Type RM Length L Ch R = 1 ,232     ,0,0,0
BEGIN DESCRIPTION:
Stream0426 0.0
END DESCRIPTION:
XS GIS Cut Line= 4
      1870070.34     13958410.07       1869818.6     13958352.78
      1869622.42     13958427.43       1869522.2     13958781.65
#Sta/Elev= 30
  4652.3 1828.23    4668 1826.28  4695.7 1826.15  4700.8 1824.93  4719.3  1827.5
  4738.7 1828.23  4741.2 1826.98  4743.8 1825.67  4760.3 1826.83  4780.8 1826.46
  4801.4 1821.35  4816.9 1815.19  4842.4 1805.43  4862.9  1799.6    4925 1796.28
  4960.7 1796.76  5008.2  1795.7  5008.5  1795.2  5012.2  1795.7  5075.8 1797.21
  5120.4 1797.08  5199.3 1799.19  5277.6 1799.14  5311.5 1800.57  5350.7 1799.86
  5389.8 1800.86  5418.6 1802.62  5429.6 1802.14  5450.4 1803.71  5488.5 1803.25
#Mann= 5 ,-1 , 0
  4652.3    .035       0  4741.2     .07       0  4816.9      .1       0
  5008.2     .05       0  5012.2      .1       0
#XS Ineff= 2 , 0
         4934.19 1802.24    5080          1801.9
Permanent Ineff=
       F       F
Bank Sta=5008.2,5012.2
XS Rating Curve= 0 ,0
Exp/Cntr=0.3,0.1

Chan Stop Cuts=-1
Use User Specified Reach Order=0
Composite Channel Slope=5