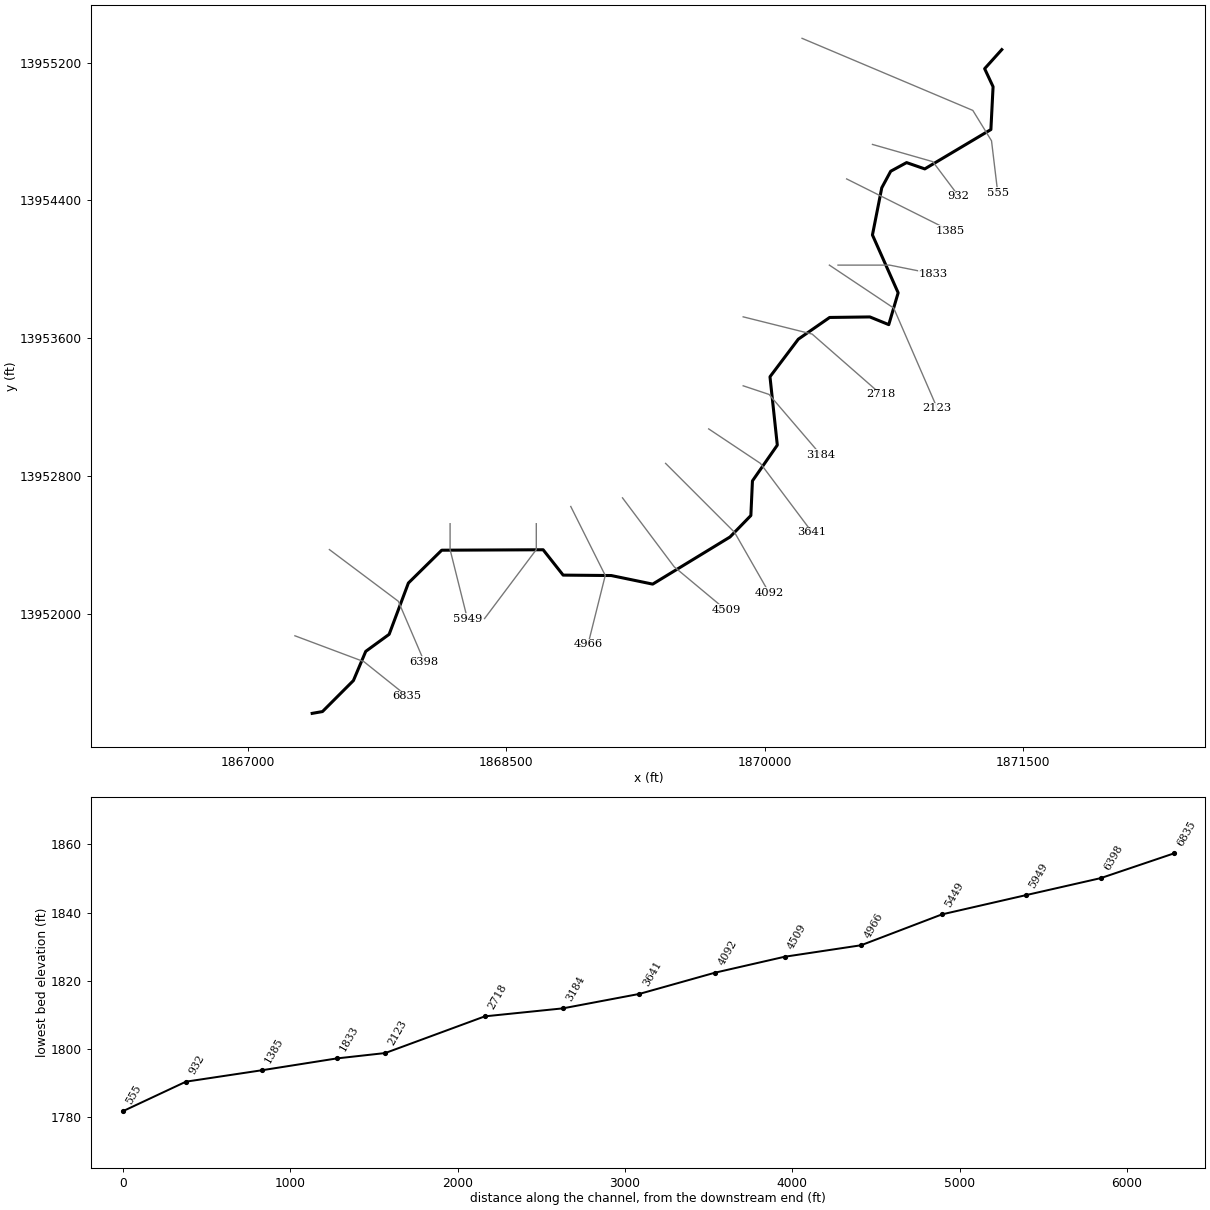
--- Stream0427.prj (project) ---

Proj Title=Stream0427 Base Level Engineering
Current Plan=p01
Default Exp/Contr=0.3,0.1
English Units
Geom File=g01
Flow File=f01
Plan File=p01
BEGIN DESCRIPTION:
Stream0427
END DESCRIPTION:

--- Stream0427.p01 (plan) ---

Plan Title=Multiple Run
Short Identifier=Multiple
Geom File=g01
Flow File=f01
Subcritical Flow
K Sum by GR= 0
Std Step Tol= 0.01
Critical Tol= 0.01
Num of Std Step Trials= 20
Max Error Tol= 0.3
Flow Tol Ratio= 0.001
Split Flow NTrial= 30
Split Flow Tol= 0.02
Split Flow Ratio= 0.02
Log Output Level= 0
Friction Slope Method= 1
Unsteady Friction Slope Method= 2
Unsteady Bridges Friction Slope Method= 1
Parabolic Critical Depth
Global Vel Dist=  1 , 1 , 1
Global Log Level= 0
CheckData=True
Encroach Param= -1, 0, 0, 0
BEGIN DESCRIPTION:
Multiple Run
END DESCRIPTION:

--- Stream0427.f01 (steady flow) ---

Flow Title=Multiple
Number of Profiles=7
Profile Names=10-year,25-year,50-year,1pct_min,100-year,1pct_plu,500-year
River Rch & RM= Stream0427,Reach-1,6835
    2261    4027    5777    3997    7975   15912   15028
Boundary for River Rch & Prof#=Stream0427,Reach-1,1
Up Type=0
Dn Type=3
Dn Slope=0.005
Boundary for River Rch & Prof#=Stream0427,Reach-1,2
Up Type=0
Dn Type=3
Dn Slope=0.005
Boundary for River Rch & Prof#=Stream0427,Reach-1,3
Up Type=0
Dn Type=3
Dn Slope=0.005
Boundary for River Rch & Prof#=Stream0427,Reach-1,4
Up Type=0
Dn Type=3
Dn Slope=0.005
Boundary for River Rch & Prof#=Stream0427,Reach-1,5
Up Type=0
Dn Type=3
Dn Slope=0.005
Boundary for River Rch & Prof#=Stream0427,Reach-1,6
Up Type=0
Dn Type=3
Dn Slope=0.005
Boundary for River Rch & Prof#=Stream0427,Reach-1,7
Up Type=0
Dn Type=3
Dn Slope=0.005

--- Stream0427.g01 (geometry) ---

Geom Title=Existing Conditions

River Reach=Stream0427,Reach-1
Reach XY= 30
      1867375.00     13951425.00      1867434.79     13951435.51
      1867614.24     13951615.32      1867685.76     13951784.70
      1867821.49     13951883.48      1867933.14     13952181.06
      1868126.46     13952371.46      1868714.72     13952374.01
      1868830.67     13952226.98      1869109.78     13952224.48
      1869350.12     13952174.71      1869798.47     13952448.01
      1869919.54     13952572.55      1869928.75     13952773.45
      1870072.94     13952980.86      1870030.47     13953377.44
      1870194.77     13953595.42      1870376.47     13953721.45
      1870609.80     13953724.46      1870719.42     13953679.76
      1870773.90     13953864.45      1870624.76     13954199.92
      1870678.81     13954473.44      1870730.58     13954569.43
      1870822.78     13954619.65      1870928.31     13954583.07
      1871311.78     13954811.33      1871324.46     13955059.79
      1871275.55     13955164.38      1871375.00     13955275.00

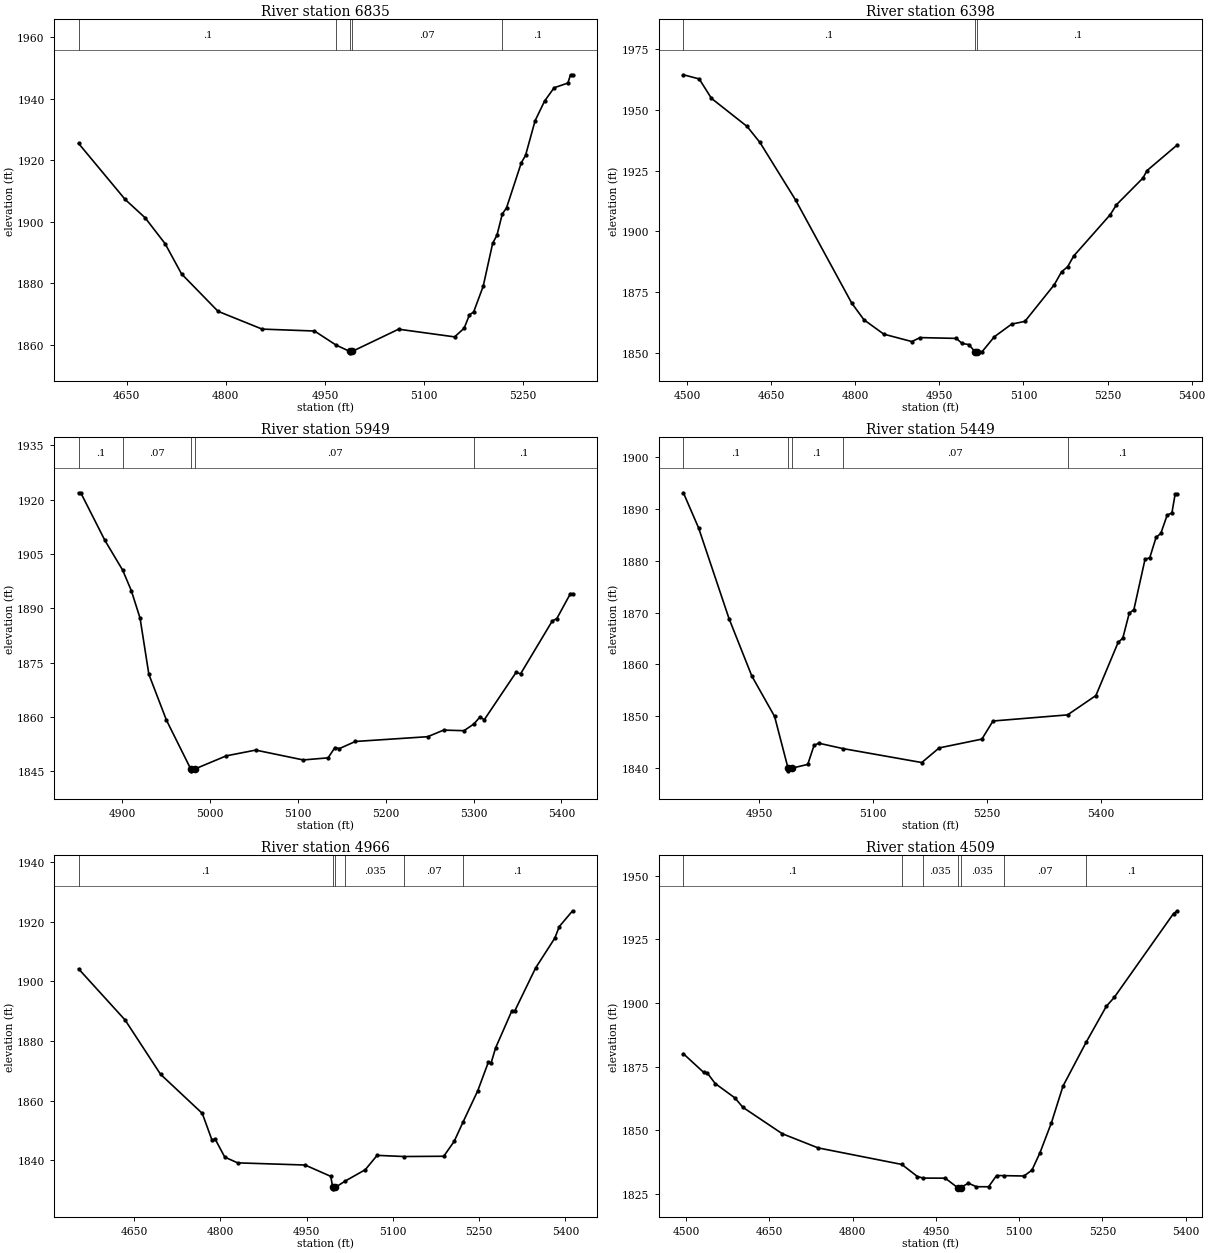
Type RM Length L Ch R = 1,6835,437,437,437
BEGIN DESCRIPTION:
Stream0427 14.0
END DESCRIPTION:
XS GIS Cut Line= 3
      1867274.96     13951875.02      1867675.00     13951725.00
      1867925.00     13951525.00
#Sta/Elev= 30
  4577.3 1925.50  4647.7 1907.28  4677.9 1901.32  4708.2 1892.88  4733.1 1883.04
  4788.3 1870.87  4855.0 1865.08  4934.2 1864.46  4966.9 1859.88  4987.2 1857.86
  4987.5 1857.36  4991.6 1857.86  5061.4 1865.05  5146.2 1862.55  5160.6 1865.37
  5168.6 1869.71  5175.0 1870.67  5189.4 1879.00  5203.8 1893.05  5210.2 1895.59
  5218.3 1902.52  5224.7 1904.53  5247.1 1919.21  5253.5 1921.60  5267.9 1932.86
  5282.3 1939.27  5296.7 1943.60  5317.5 1945.12  5321.5 1947.82  5324.7 1947.82
#Mann=5,-1,0
  4577.3     0.1       0  4966.9    0.07       0  4987.2    0.05       0
  4991.6    0.07       0  5218.3     0.1       0
Bank Sta=4987.2,4991.6
Exp/Cntr=0.3,0.1

Type RM Length L Ch R = 1,6398,449,449,449
BEGIN DESCRIPTION:
Stream0427 13.0
END DESCRIPTION:
XS GIS Cut Line= 3
      1867474.98     13952375.02      1867875.00     13952075.00
      1868024.99     13951725.02
#Sta/Elev= 30
  4493.8 1964.31  4522.0 1962.60  4543.8 1954.63  4607.4 1943.08  4630.3 1936.50
  4693.8 1912.88  4793.8 1870.58  4815.7 1863.69  4851.1 1857.79  4901.1 1854.75
  4915.7 1856.38  4980.3 1856.05  4990.7 1853.96  5002.9 1853.52  5013.3 1850.62
  5013.6 1850.12  5017.8 1850.62  5026.5 1850.65  5048.2 1856.73  5079.1 1861.93
  5102.6 1863.03  5155.2 1878.16  5167.9 1883.37  5178.8 1885.47  5189.7 1889.91
  5254.9 1906.89  5265.8 1910.93  5313.0 1921.88  5320.2 1924.94  5374.6 1935.58
#Mann=3,-1,0
  4493.8     0.1       0  5013.3    0.05       0  5017.8     0.1       0
Bank Sta=5013.3,5017.8
Exp/Cntr=0.3,0.1

Type RM Length L Ch R = 1,5949,500,500,500
BEGIN DESCRIPTION:
Stream0427 12.0
END DESCRIPTION:
XS GIS Cut Line= 3
      1868175.00     13952525.04      1868175.00     13952375.00
      1868274.99     13951975.05
#Sta/Elev= 30
  4850.4 1921.91  4852.9 1921.91  4880.4 1908.75  4900.6 1900.54  4910.4 1894.91
  4920.4 1887.28  4930.4 1871.78  4950.4 1859.12  4978.1 1845.61  4978.5 1845.11
  4982.7 1845.61  5018.5 1849.25  5052.0 1850.84  5106.1 1848.12  5134.4 1848.70
  5142.2 1851.55  5147.3 1851.26  5165.4 1853.22  5247.8 1854.54  5265.9 1856.36
  5289.1 1856.20  5300.6 1858.10  5307.1 1859.97  5312.2 1859.24  5348.3 1872.29
  5353.5 1871.91  5389.6 1886.53  5394.7 1887.16  5410.2 1894.06  5412.7 1894.06
#Mann=5,-1,0
  4850.4     0.1       0  4900.6    0.07       0  4978.1    0.05       0
  4982.7    0.07       0  5300.6     0.1       0
Bank Sta=4978.1,4982.7
Exp/Cntr=0.3,0.1

Type RM Length L Ch R = 1,5449,483,483,483
BEGIN DESCRIPTION:
Stream0427 11.0
END DESCRIPTION:
XS GIS Cut Line= 3
      1868675.00     13952525.01      1868675.00     13952375.00
      1868375.01     13951975.01
#Sta/Elev= 30
  4850.4 1893.11  4870.4 1886.33  4910.4 1868.86  4940.4 1857.78  4970.4 1849.97
  4988.1 1839.99  4988.4 1839.49  4992.7 1839.99  5014.0 1840.73  5022.3 1844.40
  5028.5 1844.82  5060.0 1843.79  5164.0 1841.09  5186.9 1843.91  5243.1 1845.61
  5257.7 1849.10  5355.8 1850.28  5393.1 1854.01  5422.3 1864.24  5428.5 1865.09
  5436.9 1869.85  5443.1 1870.60  5457.7 1880.26  5464.0 1880.61  5472.3 1884.52
  5478.5 1885.27  5486.9 1888.82  5493.1 1889.22  5497.3 1892.81  5500.4 1892.81
#Mann=5,-1,0
  4850.4     0.1       0  4988.1    0.05       0  4992.7     0.1       0
  5060.0    0.07       0  5355.8     0.1       0
Bank Sta=4988.1,4992.7
Exp/Cntr=0.3,0.1

Type RM Length L Ch R = 1,4966,457,457,457
BEGIN DESCRIPTION:
Stream0427 10.0
END DESCRIPTION:
XS GIS Cut Line= 3
      1868874.99     13952625.02      1869075.00     13952225.00
      1868975.01     13951825.04
#Sta/Elev= 30
  4553.2 1904.18  4634.3 1887.00  4695.8 1868.85  4768.4 1855.74  4785.2 1846.85
  4790.8 1847.12  4807.6 1841.07  4829.9 1839.16  4947.3 1838.43  4992.0 1834.63
  4995.3 1830.95  4995.6 1830.45  5000.0 1830.95  5017.4 1833.10  5052.0 1836.86
  5072.6 1841.67  5119.6 1841.28  5188.5 1841.37  5206.6 1846.35  5221.8 1852.72
  5247.8 1863.38  5265.9 1872.80  5271.0 1872.71  5278.7 1877.68  5307.1 1890.16
  5312.2 1890.13  5348.3 1904.47  5381.8 1914.50  5389.5 1918.35  5412.7 1923.64
#Mann=6,-1,0
  4553.2     0.1       0  4995.3    0.05       0  5000.0     0.1       0
  5017.4   0.035       0  5119.6    0.07       0  5221.8     0.1       0
Bank Sta=4995.3,5000
Exp/Cntr=0.3,0.1

Type RM Length L Ch R = 1,4509,417,417,417
BEGIN DESCRIPTION:
Stream0427 9.0
END DESCRIPTION:
XS GIS Cut Line= 3
      1869174.99     13952675.02      1869475.00     13952275.00
      1869774.97     13952025.02
#Sta/Elev= 30
  4494.9 1880.11  4531.4 1872.81  4537.6 1872.66  4552.2 1868.43  4587.6 1862.80
  4602.2 1859.07  4673.0 1848.73  4737.6 1843.16  4888.6 1836.66  4916.8 1831.90
  4927.4 1831.30  4966.8 1831.27  4989.0 1827.58  4989.5 1827.08  4994.5 1827.58
  5008.6 1829.31  5022.9 1827.91  5045.0 1827.90  5059.4 1832.31  5072.6 1832.26
  5108.8 1832.12  5123.1 1834.41  5137.5 1841.19  5158.3 1853.07  5179.1 1867.42
  5220.6 1884.55  5257.2 1898.74  5271.5 1902.24  5378.3 1935.16  5385.4 1936.24
#Mann=7,-1,0
  4494.9     0.1       0  4888.6    0.07       0  4927.4   0.035       0
  4989.0   0.035       0  4994.5   0.035       0  5072.6    0.07       0
  5220.6     0.1       0
Bank Sta=4989,4994.5
Exp/Cntr=0.3,0.1

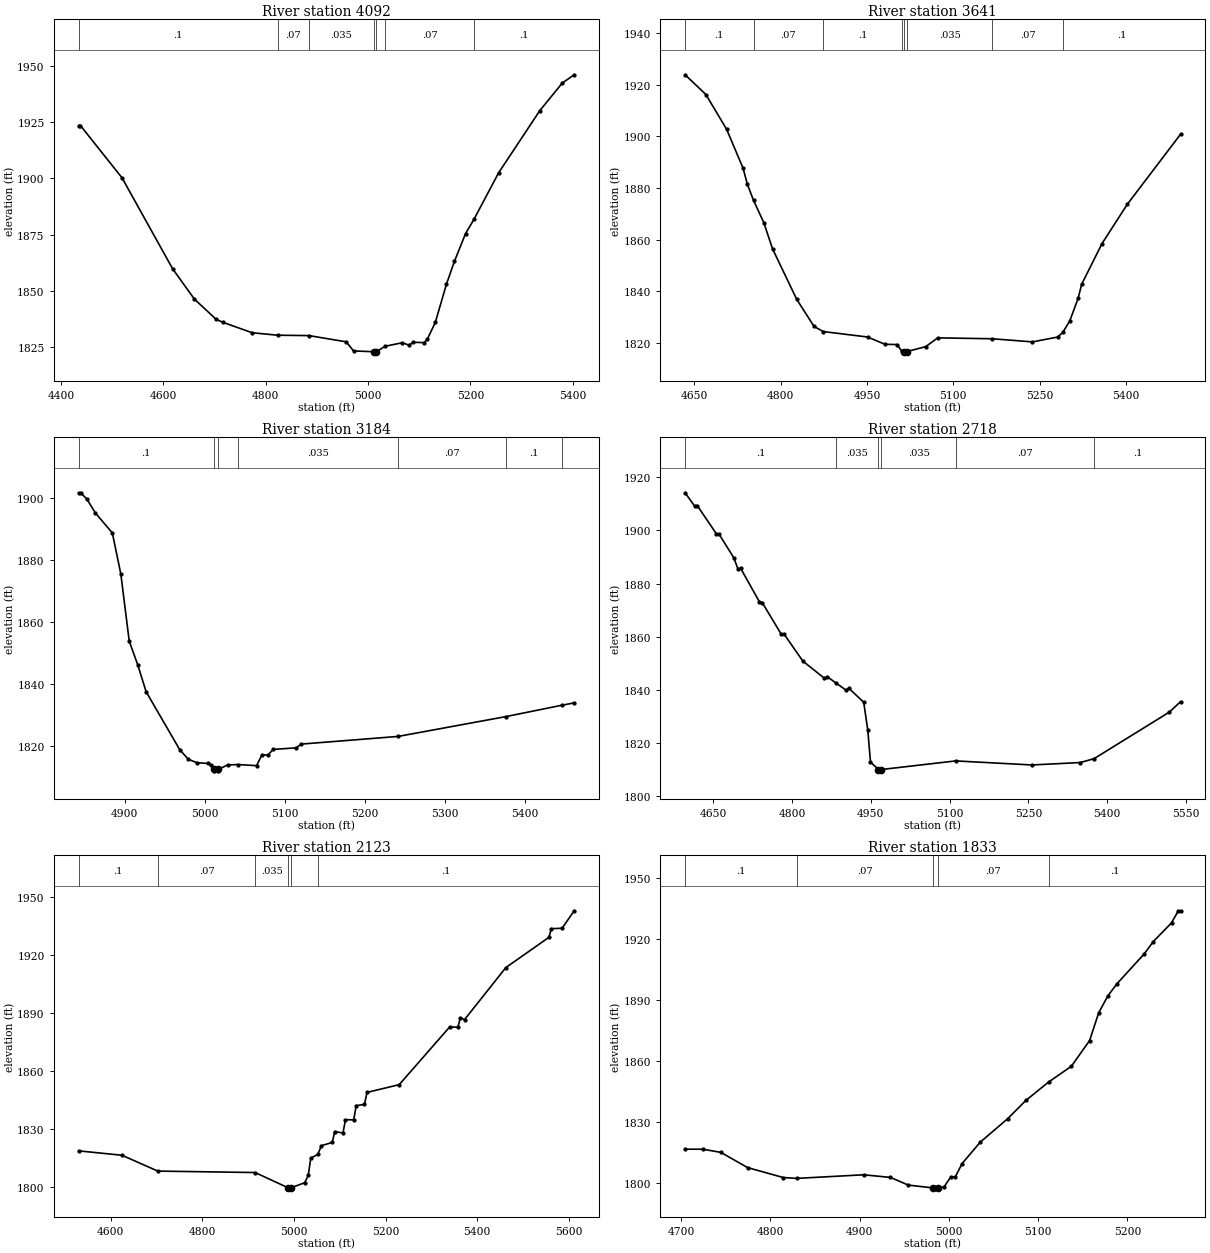
Type RM Length L Ch R = 1,4092,451,451,451
BEGIN DESCRIPTION:
Stream0427 8.0
END DESCRIPTION:
XS GIS Cut Line= 3
      1869425.02     13952874.98      1869825.00     13952475.00
      1870025.01     13952124.98
#Sta/Elev= 30
  4434.1 1923.50  4437.6 1923.50  4518.9 1900.26  4617.9 1859.78  4660.3 1846.34
  4702.8 1837.32  4716.9 1835.91  4773.5 1831.33  4823.0 1830.24  4884.3 1830.07
  4957.3 1827.30  4971.5 1823.25  5010.7 1822.90  5011.1 1822.40  5016.2 1822.90
  5033.4 1825.34  5066.7 1826.88  5080.4 1825.83  5088.3 1827.10  5109.9 1826.94
  5115.7 1828.42  5131.5 1835.97  5153.1 1852.89  5168.9 1863.15  5190.5 1875.42
  5207.1 1881.84  5255.3 1902.52  5335.9 1930.19  5379.8 1942.44  5402.9 1946.08
#Mann=7,-1,0
  4434.1     0.1       0  4823.0    0.07       0  4884.3   0.035       0
  5010.7   0.035       0  5016.2   0.035       0  5033.4    0.07       0
  5207.1     0.1       0
Bank Sta=5010.7,5016.2
Exp/Cntr=0.3,0.1

Type RM Length L Ch R = 1,3641,457,457,457
BEGIN DESCRIPTION:
Stream0427 7.0
END DESCRIPTION:
XS GIS Cut Line= 3
      1869674.97     13953075.02      1869975.00     13952875.00
      1870275.00     13952475.00
#Sta/Elev= 30
  4634.2 1923.88  4670.3 1916.24  4706.4 1902.73  4734.9 1887.67  4742.4 1881.42
  4753.0 1875.26  4771.0 1866.56  4786.0 1856.51  4828.0 1836.93  4858.1 1826.43
  4874.1 1824.43  4951.2 1822.32  4981.3 1819.50  5002.1 1819.40  5010.3 1816.94
  5013.9 1816.69  5014.4 1816.19  5019.4 1816.69  5052.1 1818.59  5072.9 1821.99
  5168.0 1821.64  5237.5 1820.43  5281.3 1822.31  5290.1 1824.10  5302.1 1828.49
  5316.7 1837.24  5322.9 1842.75  5358.3 1858.52  5402.1 1873.70  5494.8 1900.89
#Mann=8,-1,0
  4634.2     0.1       0  4753.0    0.07       0  4874.1     0.1       0
  5010.3   0.035       0  5013.9    0.05       0  5019.4   0.035       0
  5168.0    0.07       0  5290.1     0.1       0
Bank Sta=5013.9,5019.4
Exp/Cntr=0.3,0.1

Type RM Length L Ch R = 1,3184,466,466,466
BEGIN DESCRIPTION:
Stream0427 6.0
END DESCRIPTION:
XS GIS Cut Line= 3
      1869875.04     13953324.99      1870025.00     13953275.00
      1870324.97     13952925.04
#Sta/Elev= 30
  4842.4 1901.65  4845.0 1901.65  4852.9 1899.55  4863.4 1895.11  4884.5 1888.71
  4895.1 1875.47  4905.6 1853.80  4916.1 1846.26  4926.7 1837.48  4968.8 1818.73
  4979.4 1815.71  4989.9 1814.59  5003.8 1814.35  5007.6 1813.86  5011.3 1812.46
  5011.8 1811.96  5016.6 1811.96  5017.0 1812.46  5028.5 1813.85  5041.6 1813.99
  5064.7 1813.63  5071.3 1817.09  5078.9 1817.10  5085.5 1818.87  5114.1 1819.38
  5120.7 1820.59  5241.4 1823.06  5376.2 1829.46  5445.8 1833.11  5461.4 1833.88
#Mann=7,-1,0
  4842.4     0.1       0  5011.3    0.05       0  5017.0     0.1       0
  5041.6   0.035       0  5241.4    0.07       0  5376.2     0.1       0
  5445.8    0.07       0
Bank Sta=5011.3,5017
Exp/Cntr=0.3,0.1

Type RM Length L Ch R = 1,2718,595,595,595
BEGIN DESCRIPTION:
Stream0427 5.0
END DESCRIPTION:
XS GIS Cut Line= 3
      1869874.99     13953725.00      1870275.00     13953625.00
      1870674.98     13953275.02
#Sta/Elev= 30
  4596.2 1914.10  4614.3 1909.12  4619.4 1909.28  4655.5 1898.76  4660.6 1898.64
  4689.0 1889.66  4696.7 1885.58  4701.9 1885.75  4737.9 1873.07  4743.1 1872.84
  4779.2 1861.01  4784.3 1861.11  4820.4 1850.87  4861.6 1844.38  4866.8 1845.04
  4883.0 1842.70  4902.9 1839.91  4908.0 1840.66  4936.4 1835.39  4944.1 1825.00
  4949.3 1812.93  4964.4 1810.12  4964.9 1809.62  4970.1 1810.12  5111.6 1813.35
  5256.7 1811.83  5348.8 1812.74  5375.0 1814.18  5518.7 1831.71  5540.0 1835.63
#Mann=6,-1,0
  4596.2     0.1       0  4883.0   0.035       0  4964.4   0.035       0
  4970.1   0.035       0  5111.6    0.07       0  5375.0     0.1       0
Bank Sta=4964.4,4970.1
Exp/Cntr=0.3,0.1

Type RM Length L Ch R = 1,2123,290,290,290
BEGIN DESCRIPTION:
Stream0427 4.0
END DESCRIPTION:
XS GIS Cut Line= 3
      1870374.99     13954025.01      1870748.12     13953775.94
      1871000.36     13953195.50
#Sta/Elev= 30
  4530.2 1818.56  4624.8 1816.28  4703.0 1808.07  4915.4 1807.32  4987.8 1799.37
  4988.3 1798.87  4993.6 1799.37  5023.5 1802.05  5031.3 1805.81  5036.8 1814.79
  5052.1 1816.70  5060.2 1821.25  5083.7 1822.93  5089.1 1828.54  5107.1 1827.84
  5112.6 1834.71  5130.6 1834.62  5136.0 1842.03  5154.0 1842.62  5159.5 1848.85
  5229.8 1852.88  5340.0 1882.79  5358.0 1882.69  5363.4 1887.59  5372.4 1886.58
  5462.6 1913.58  5556.4 1929.21  5561.9 1933.74  5585.3 1933.96  5611.7 1943.02
#Mann=6,-1,0
  4530.2     0.1       0  4703.0    0.07       0  4915.4   0.035       0
  4987.8   0.035       0  4993.6   0.035       0  5052.1     0.1       0
Bank Sta=4987.8,4993.6
Exp/Cntr=0.3,0.1

Type RM Length L Ch R = 1,1833,448,448,448
BEGIN DESCRIPTION:
Stream0427 3.0
END DESCRIPTION:
XS GIS Cut Line= 3
      1870424.99     13954025.00      1870725.00     13954025.00
      1870975.03     13953974.99
#Sta/Elev= 30
  4704.6 1816.76  4724.6 1816.71  4744.6 1815.19  4774.6 1807.70  4814.6 1802.83
  4829.6 1802.42  4904.6 1804.18  4934.6 1802.90  4954.6 1799.12  4981.7 1797.79
  4982.2 1797.29  4987.5 1797.79  4994.6 1798.19  5002.1 1803.14  5007.2 1803.14
  5014.8 1809.68  5035.2 1820.20  5065.8 1831.66  5086.2 1840.64  5111.8 1849.70
  5137.2 1857.40  5157.6 1870.01  5167.8 1883.60  5178.0 1891.88  5188.2 1897.85
  5218.8 1912.55  5229.0 1918.59  5249.4 1927.77  5257.0 1933.69  5259.6 1933.69
#Mann=5,-1,0
  4704.6     0.1       0  4829.6    0.07       0  4981.7   0.035       0
  4987.5    0.07       0  5111.8     0.1       0
Bank Sta=4981.7,4987.5
Exp/Cntr=0.3,0.1

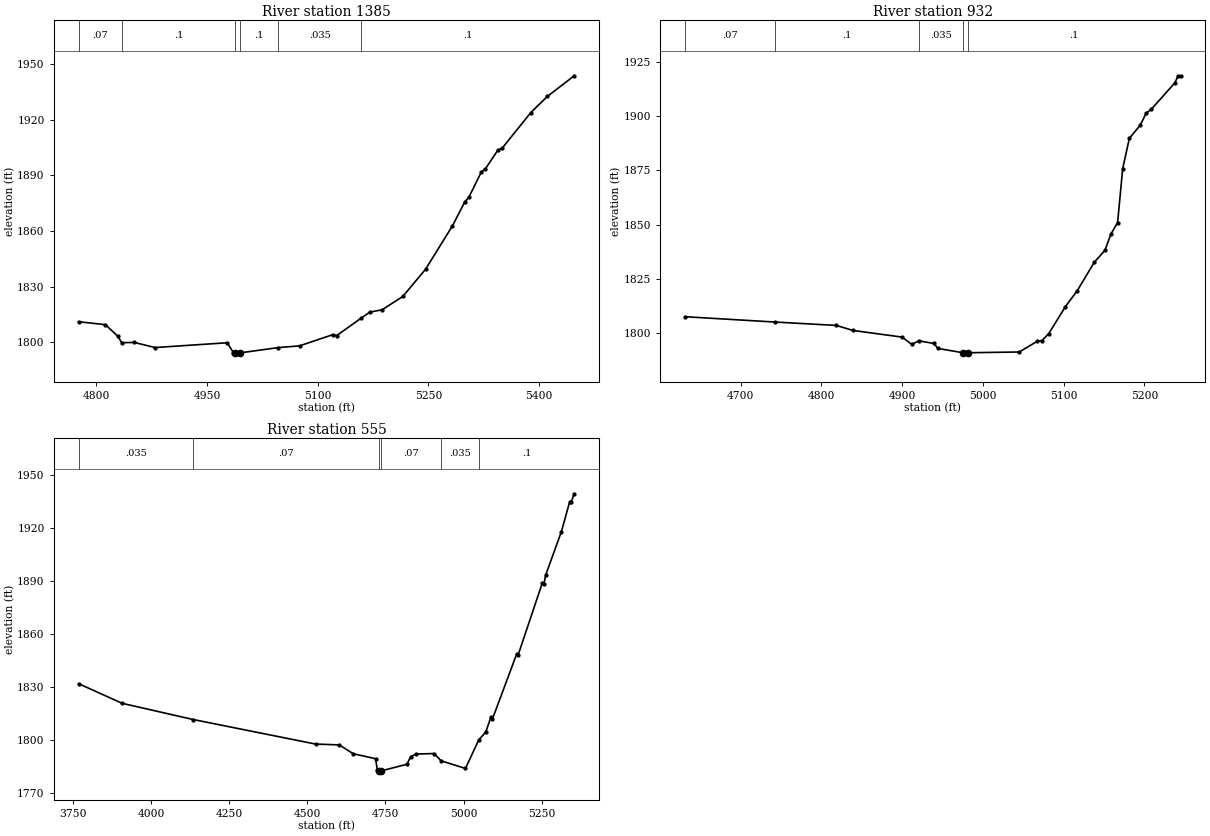
Type RM Length L Ch R = 1,1385,453,453,453
BEGIN DESCRIPTION:
Stream0427 2.0
END DESCRIPTION:
XS GIS Cut Line= 3
      1870475.00     13954525.00      1870675.00     13954425.00
      1871074.98     13954225.01
#Sta/Elev= 30
  4776.4 1811.11  4812.7 1809.52  4829.5 1803.27  4834.7 1799.84  4851.9 1799.95
  4879.8 1797.21  4977.6 1799.79  4986.0 1794.34  4988.7 1794.32  4989.2 1793.82
  4994.5 1794.32  5046.5 1797.18  5075.5 1798.12  5120.2 1804.12  5125.8 1803.66
  5158.5 1812.95  5170.5 1816.27  5187.3 1817.56  5215.2 1824.71  5246.0 1839.35
  5282.3 1862.65  5299.1 1875.61  5304.7 1878.18  5321.4 1891.65  5327.0 1893.42
  5343.8 1903.44  5349.4 1904.40  5388.5 1923.75  5410.9 1932.41  5447.2 1943.55
#Mann=6,-1,0
  4776.4    0.07       0  4834.7     0.1       0  4988.7    0.05       0
  4994.5     0.1       0  5046.5   0.035       0  5158.5     0.1       0
Bank Sta=4988.7,4994.5
Exp/Cntr=0.3,0.1

Type RM Length L Ch R = 1,932,377,377,377
BEGIN DESCRIPTION:
Stream0427 1.0
END DESCRIPTION:
XS GIS Cut Line= 3
      1870624.96     13954725.01      1870975.00     13954625.00
      1871124.97     13954425.04
#Sta/Elev= 30
  4631.0 1807.57  4743.0 1805.10  4818.2 1803.57  4839.0 1801.25  4900.1 1798.17
  4911.8 1794.82  4920.8 1796.48  4939.1 1795.25  4944.3 1792.98  4975.2 1790.98
  4975.7 1790.48  4981.1 1790.98  5045.0 1791.33  5066.9 1796.17  5073.2 1796.61
  5081.5 1799.75  5102.3 1812.25  5116.9 1819.54  5137.8 1832.53  5151.3 1838.19
  5158.6 1845.60  5166.9 1850.93  5173.2 1875.74  5181.5 1889.70  5195.0 1895.75
  5202.3 1901.29  5208.6 1903.03  5237.8 1915.22  5241.9 1918.48  5245.0 1918.48
#Mann=5,-1,0
  4631.0    0.07       0  4743.0     0.1       0  4920.8   0.035       0
  4975.2    0.05       0  4981.1     0.1       0
Bank Sta=4975.2,4981.1
Exp/Cntr=0.3,0.1

Type RM Length L Ch R = 1,555,0,0,0
BEGIN DESCRIPTION:
Stream0427 0.0
END DESCRIPTION:
XS GIS Cut Line= 4
      1870216.54     13955340.40      1871207.03     13954922.31
      1871315.44     13954745.99      1871351.64     13954444.45
#Sta/Elev= 30
  3768.2 1831.71  3907.6 1820.60  4134.6 1811.44  4526.3 1797.54  4602.3 1797.07
  4647.3 1792.05  4718.5 1789.25  4723.9 1783.03  4729.6 1782.32  4730.1 1781.82
  4735.5 1782.32  4818.8 1786.10  4830.3 1790.27  4847.5 1791.87  4905.5 1792.19
  4928.4 1788.05  5006.1 1783.74  5048.4 1799.82  5071.4 1804.50  5087.6 1812.85
  5092.6 1811.78  5169.8 1848.42  5174.8 1848.05  5252.0 1888.69  5257.1 1887.89
  5262.8 1893.20  5313.2 1917.82  5339.3 1934.48  5344.3 1934.33  5354.0 1939.21
#Mann=6,-1,0
  3768.2   0.035       0  4134.6    0.07       0  4729.6   0.035       0
  4735.5    0.07       0  4928.4   0.035       0  5048.4     0.1       0
Bank Sta=4729.6,4735.5
Exp/Cntr=0.3,0.1

Chan Stop Cuts=-1