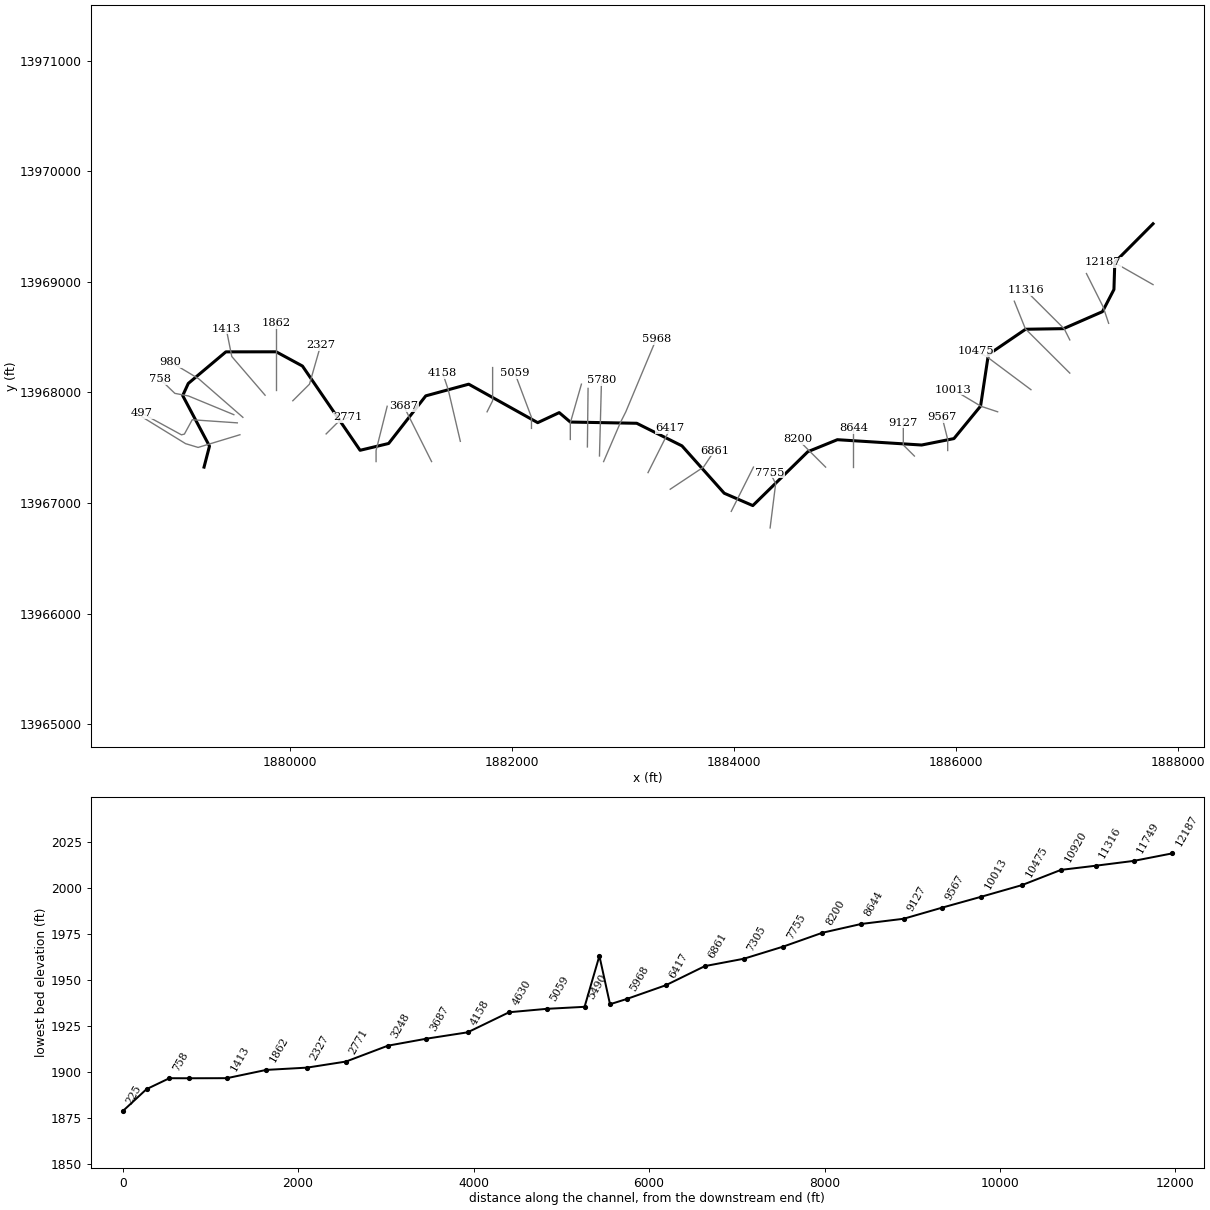
--- Stream0431.prj (project) ---

Proj Title=Stream0431 Base Level Engineering
Current Plan=p01
Default Exp/Contr=0.3,0.1
English Units
Geom File=g01
Flow File=f01
Plan File=p01
BEGIN DESCRIPTION:
Stream0431
END DESCRIPTION:

--- Stream0431.p01 (plan) ---

Plan Title=Multiple Run
Short Identifier=Multiple
Geom File=g01
Flow File=f01
Subcritical Flow
K Sum by GR= 0
Std Step Tol= 0.01
Critical Tol= 0.01
Num of Std Step Trials= 20
Max Error Tol= 0.3
Flow Tol Ratio= 0.001
Split Flow NTrial= 30
Split Flow Tol= 0.02
Split Flow Ratio= 0.02
Log Output Level= 0
Friction Slope Method= 1
Unsteady Friction Slope Method= 2
Unsteady Bridges Friction Slope Method= 1
Parabolic Critical Depth
Global Vel Dist=  1 , 1 , 1
Global Log Level= 0
CheckData=True
Encroach Param= -1, 0, 0, 0
BEGIN DESCRIPTION:
Multiple Run
END DESCRIPTION:

--- Stream0431.f01 (steady flow) ---

Flow Title=Multiple
Number of Profiles=7
Profile Names=10-year,25-year,50-year,1pct_min,100-year,1pct_plu,500-year
River Rch & RM= Stream0431,Reach-1,12187
    2335    4131    5897    4056    8092   16146   15074
River Rch & RM= Stream0431,Reach-1,5659
    2888    5161    7417    5131   10239   20429   19303
River Rch & RM= Stream0431,Reach-1,2327
    3069    5501    7920    5490   10953   21855   20725
Boundary for River Rch & Prof#=Stream0431,Reach-1,1
Up Type=0
Dn Type=3
Dn Slope=0.005
Boundary for River Rch & Prof#=Stream0431,Reach-1,2
Up Type=0
Dn Type=3
Dn Slope=0.005
Boundary for River Rch & Prof#=Stream0431,Reach-1,3
Up Type=0
Dn Type=3
Dn Slope=0.005
Boundary for River Rch & Prof#=Stream0431,Reach-1,4
Up Type=0
Dn Type=3
Dn Slope=0.005
Boundary for River Rch & Prof#=Stream0431,Reach-1,5
Up Type=0
Dn Type=3
Dn Slope=0.005
Boundary for River Rch & Prof#=Stream0431,Reach-1,6
Up Type=0
Dn Type=3
Dn Slope=0.005
Boundary for River Rch & Prof#=Stream0431,Reach-1,7
Up Type=0
Dn Type=3
Dn Slope=0.005

--- Stream0431.g01 (geometry) ---

Geom Title=Existing Conditions

River Reach=Stream0431,Reach-1
Reach XY= 30
      1887775.00     13969525.00      1887430.46     13969177.45
      1887422.76     13968930.93      1887319.42     13968730.58
      1886968.87     13968576.84      1886626.50     13968571.39
      1886291.28     13968342.14      1886221.25     13967876.55
      1885981.17     13967582.86      1885690.20     13967524.63
      1884930.97     13967572.83      1884665.00     13967464.37
      1884169.11     13966976.96      1883911.79     13967088.63
      1883531.06     13967516.86      1883123.45     13967721.25
      1882524.90     13967732.34      1882425.09     13967817.69
      1882231.11     13967726.79      1881609.78     13968074.75
      1881222.69     13967969.18      1880888.24     13967538.61
      1880630.86     13967477.05      1880111.74     13968238.66
      1879875.01     13968367.47      1879421.68     13968366.96
      1879083.00     13968081.33      1879032.78     13967971.60
      1879274.06     13967514.52      1879225.00     13967325.00

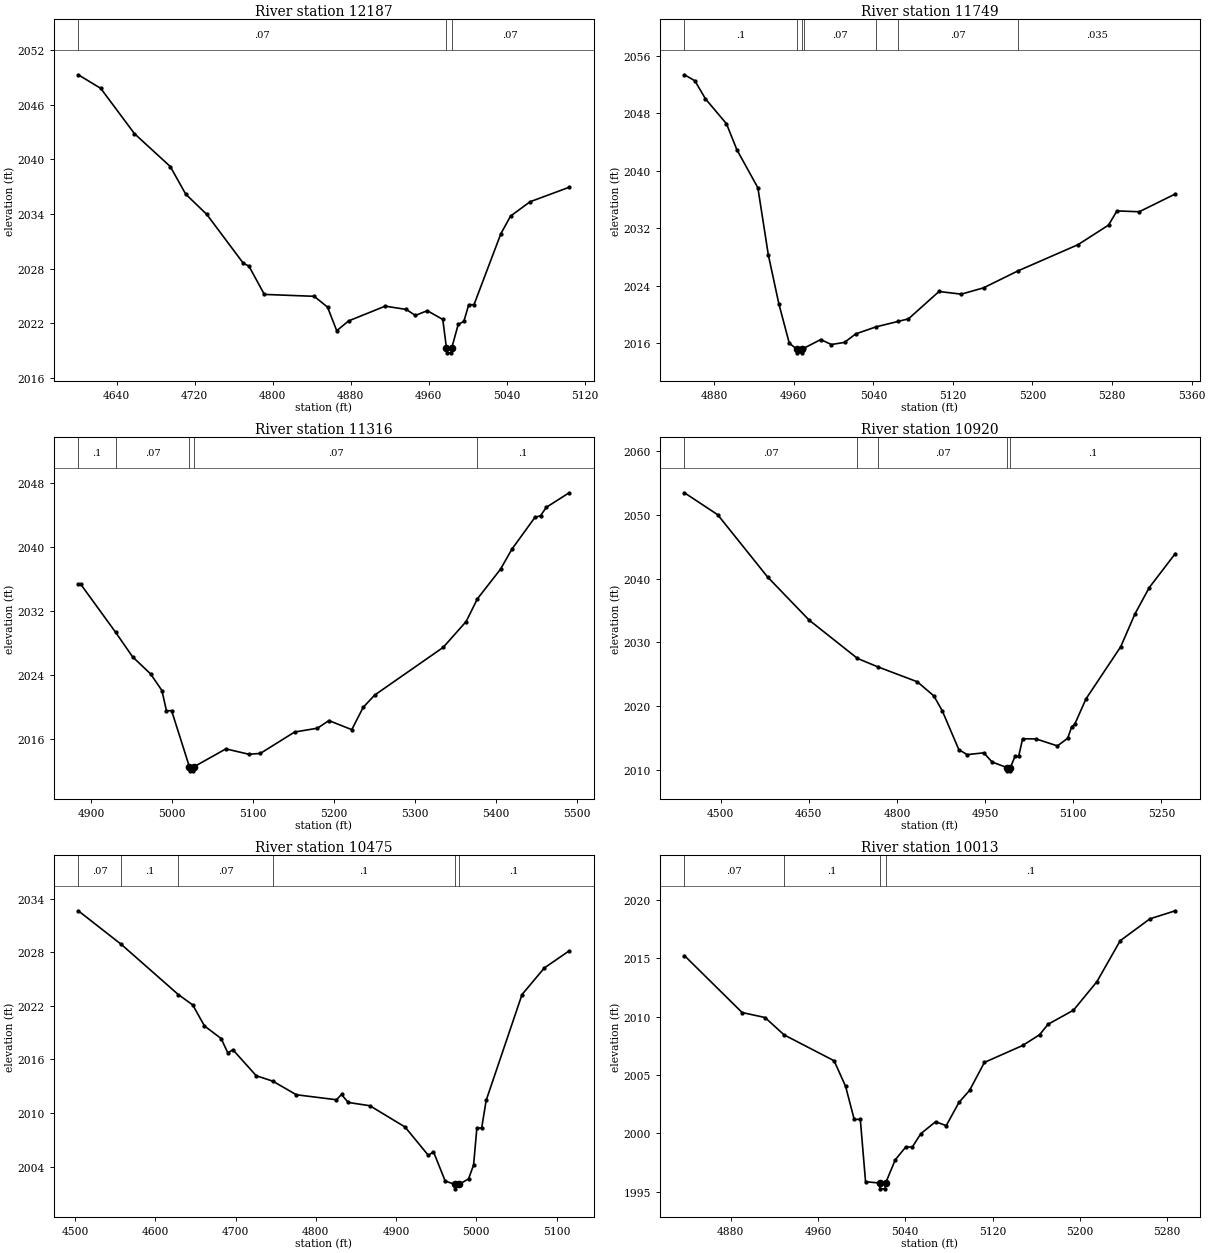
Type RM Length L Ch R = 1,12187,438,438,438
BEGIN DESCRIPTION:
Stream0431 27.0
END DESCRIPTION:
XS GIS Cut Line= 3
      1887774.98     13968975.01      1887425.00     13969175.00
      1887324.99     13969175.00
#Sta/Elev= 30
  4600.8 2049.30  4623.8 2047.81  4658.4 2042.83  4695.1 2039.22  4710.9 2036.19
  4732.5 2033.96  4769.9 2028.60  4775.7 2028.28  4791.5 2025.17  4842.6 2024.96
  4856.3 2023.77  4865.7 2021.18  4877.9 2022.26  4915.4 2023.88  4936.9 2023.52
  4946.3 2022.86  4958.5 2023.38  4974.4 2022.42  4978.2 2019.25  4978.6 2018.75
  4983.1 2018.75  4983.5 2019.25  4990.2 2021.87  4996.0 2022.21  5001.0 2024.04
  5006.4 2024.04  5033.9 2031.83  5043.9 2033.78  5063.9 2035.35  5103.9 2036.94
#Mann=3,-1,0
  4600.8    0.07       0  4978.2    0.05       0  4983.5    0.07       0
Bank Sta=4978.2,4983.5
Exp/Cntr=0.3,0.1

Type RM Length L Ch R = 1,11749,433,433,433
BEGIN DESCRIPTION:
Stream0431 26.0
END DESCRIPTION:
XS GIS Cut Line= 3
      1887375.00     13968625.01      1887325.00     13968775.00
      1887175.01     13969074.99
#Sta/Elev= 30
  4850.1 2053.39  4860.6 2052.55  4871.2 2050.04  4892.3 2046.58  4902.8 2042.95
  4923.9 2037.66  4934.4 2028.32  4945.0 2021.50  4955.5 2016.01  4963.3 2015.18
  4963.7 2014.68  4968.3 2014.68  4968.7 2015.18  4970.1 2015.32  4987.1 2016.53
  4997.7 2015.84  5011.0 2016.13  5022.2 2017.31  5042.3 2018.28  5064.7 2019.05
  5075.3 2019.41  5106.0 2023.22  5128.4 2022.85  5150.8 2023.73  5185.1 2026.07
  5245.8 2029.74  5276.5 2032.47  5284.9 2034.44  5307.3 2034.32  5343.6 2036.80
#Mann=7,-1,0
  4850.1     0.1       0  4963.3    0.05       0  4968.7     0.1       0
  4970.1    0.07       0  5042.3   0.035       0  5064.7    0.07       0
  5185.1   0.035       0
Bank Sta=4963.3,4968.7
Exp/Cntr=0.3,0.1

Type RM Length L Ch R = 1,11316,396,396,396
BEGIN DESCRIPTION:
Stream0431 25.0
END DESCRIPTION:
XS GIS Cut Line= 3
      1887025.01     13968474.97      1886975.00     13968575.00
      1886625.00     13968925.00
#Sta/Elev= 30
  4884.0 2035.37  4886.8 2035.37  4930.2 2029.34  4951.1 2026.29  4973.5 2024.14
  4987.4 2022.08  4993.0 2019.56  4999.4 2019.56  5021.4 2012.56  5021.8 2012.06
  5026.4 2012.06  5026.9 2012.56  5066.5 2014.80  5094.8 2014.13  5109.0 2014.23
  5151.4 2016.90  5179.7 2017.38  5193.8 2018.33  5222.1 2017.20  5236.2 2019.98
  5250.4 2021.51  5335.2 2027.47  5363.5 2030.69  5377.4 2033.52  5406.0 2037.22
  5420.1 2039.72  5448.4 2043.67  5455.5 2043.89  5462.5 2044.93  5490.8 2046.75
#Mann=5,-1,0
  4884.0     0.1       0  4930.2    0.07       0  5021.4    0.05       0
  5026.9    0.07       0  5377.4     0.1       0
Bank Sta=5021.4,5026.9
Exp/Cntr=0.3,0.1

Type RM Length L Ch R = 1,10920,445,445,445
BEGIN DESCRIPTION:
Stream0431 24.0
END DESCRIPTION:
XS GIS Cut Line= 3
      1887024.98     13968175.02      1886625.00     13968575.00
      1886525.01     13968824.98
#Sta/Elev= 30
  4438.7 2053.51  4495.2 2050.06  4580.1 2040.27  4650.8 2033.49  4733.0 2027.47
  4767.5 2026.15  4834.7 2023.80  4862.9 2021.58  4877.1 2019.25  4905.4 2013.13
  4919.5 2012.35  4947.8 2012.63  4961.9 2011.19  4987.5 2010.30  4987.9 2009.80
  4992.5 2009.80  4993.0 2010.30  5000.8 2012.06  5007.1 2012.06  5013.8 2014.84
  5036.7 2014.82  5073.0 2013.72  5090.5 2014.92  5097.3 2016.71  5102.6 2017.14
  5121.5 2021.09  5180.7 2029.31  5205.0 2034.48  5229.2 2038.60  5273.6 2043.96
#Mann=5,-1,0
  4438.7    0.07       0  4733.0     0.1       0  4767.5    0.07       0
  4987.5    0.05       0  4993.0     0.1       0
Bank Sta=4987.5,4993
Exp/Cntr=0.3,0.1

Type RM Length L Ch R = 1,10475,462,462,462
BEGIN DESCRIPTION:
Stream0431 23.0
END DESCRIPTION:
XS GIS Cut Line= 3
      1886674.98     13968025.02      1886275.00     13968325.00
      1886174.98     13968375.01
#Sta/Elev= 30
  4503.9 2032.64  4557.5 2028.88  4628.5 2023.27  4646.6 2022.10  4661.2 2019.75
  4682.0 2018.34  4690.3 2016.73  4696.6 2017.09  4725.7 2014.18  4746.4 2013.57
  4775.7 2012.05  4825.7 2011.49  4832.0 2012.08  4840.3 2011.19  4867.4 2010.82
  4911.2 2008.44  4940.3 2005.26  4946.6 2005.68  4961.2 2002.40  4973.0 2002.02
  4973.4 2001.52  4978.5 2002.02  4990.3 2002.63  4996.6 2004.18  5000.7 2008.33
  5006.7 2008.33  5012.3 2011.42  5057.0 2023.27  5084.9 2026.25  5115.7 2028.15
#Mann=6,-1,0
  4503.9    0.07       0  4557.5     0.1       0  4628.5    0.07       0
  4746.4     0.1       0  4973.0    0.05       0  4978.5     0.1       0
Bank Sta=4973,4978.5
Exp/Cntr=0.3,0.1

Type RM Length L Ch R = 1,10013,446,446,446
BEGIN DESCRIPTION:
Stream0431 22.0
END DESCRIPTION:
XS GIS Cut Line= 3
      1886375.04     13967824.99      1886225.00     13967875.00
      1885975.01     13968025.00
#Sta/Elev= 30
  4837.7 2015.24  4890.5 2010.36  4911.5 2009.93  4929.0 2008.44  4974.8 2006.22
  4985.3 2004.03  4993.2 2001.19  4998.8 2001.19  5003.6 1995.84  5016.4 1995.73
  5016.8 1995.23  5021.5 1995.23  5022.0 1995.73  5030.8 1997.72  5040.6 1998.84
  5046.4 1998.81  5054.2 1999.96  5067.8 2000.99  5077.5 2000.65  5089.2 2002.65
  5098.9 2003.68  5112.5 2006.08  5147.5 2007.53  5163.0 2008.45  5170.8 2009.35
  5194.1 2010.56  5215.5 2013.00  5236.9 2016.52  5264.1 2018.40  5287.4 2019.09
#Mann=4,-1,0
  4837.7    0.07       0  4929.0     0.1       0  5016.4    0.05       0
  5022.0     0.1       0
Bank Sta=5016.4,5022
Exp/Cntr=0.3,0.1

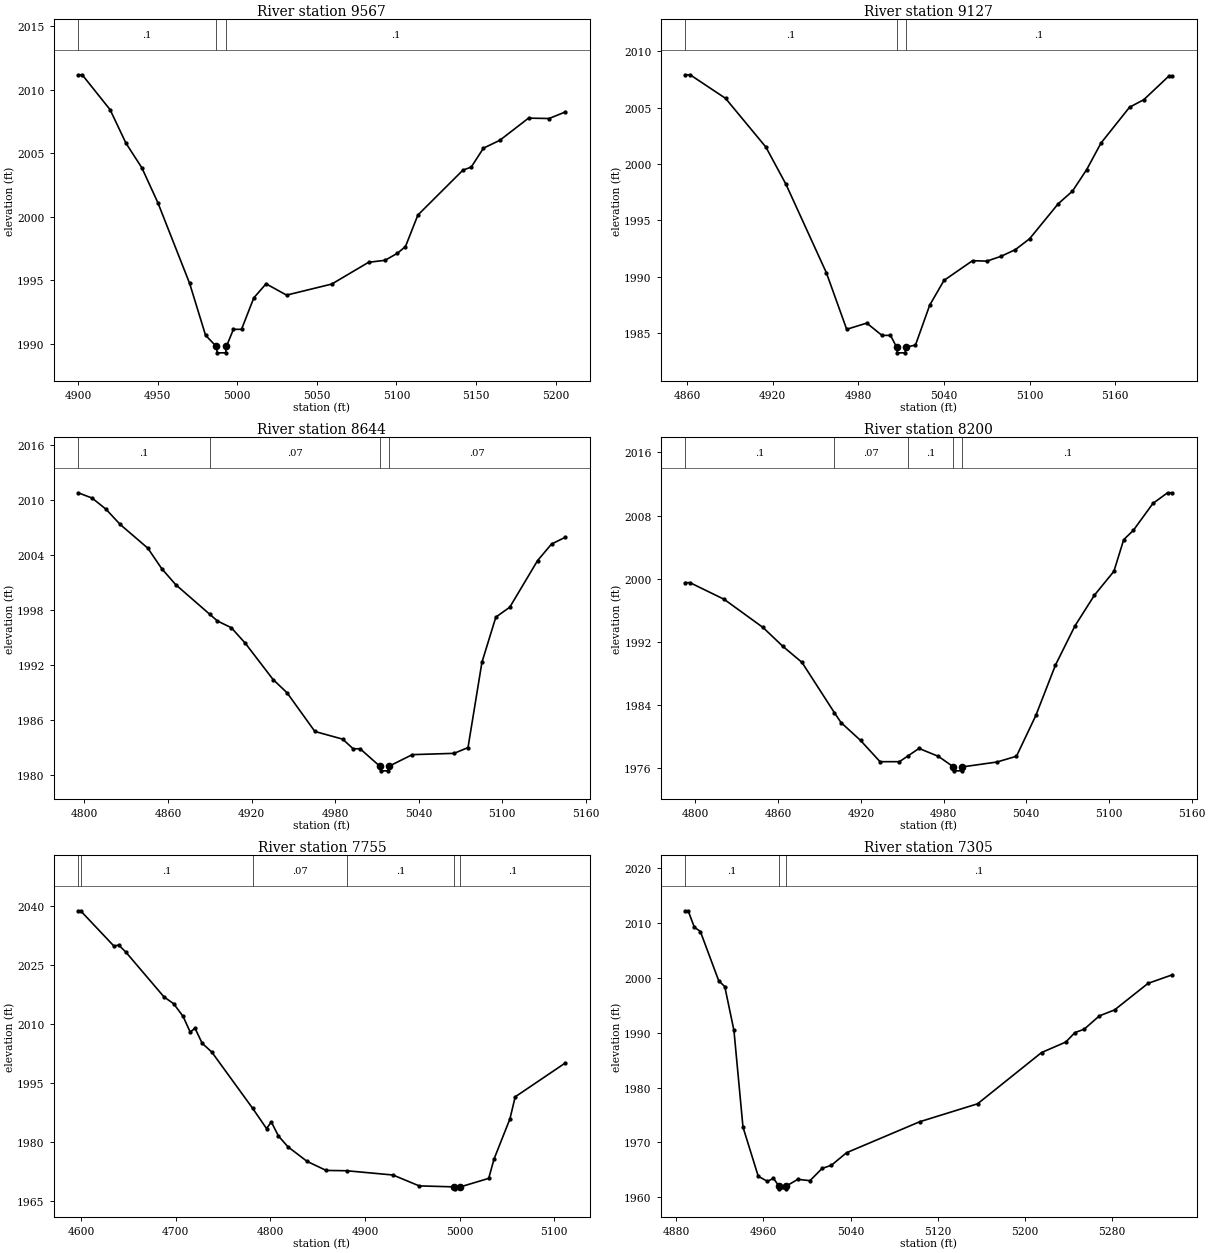
Type RM Length L Ch R = 1,9567,440,440,440
BEGIN DESCRIPTION:
Stream0431 21.0
END DESCRIPTION:
XS GIS Cut Line= 3
      1885925.00     13967475.01      1885925.00     13967575.00
      1885875.01     13967774.96
#Sta/Elev= 30
  4900.1 2011.18  4902.6 2011.18  4920.1 2008.44  4930.1 2005.80  4940.1 2003.86
  4950.1 2001.13  4970.1 1994.77  4980.1 1990.69  4986.9 1989.81  4987.4 1989.31
  4992.7 1989.31  4993.2 1989.81  4997.6 1991.16  5002.7 1991.16  5010.4 1993.63
  5018.1 1994.74  5031.0 1993.85  5059.4 1994.72  5082.5 1996.43  5092.9 1996.59
  5100.6 1997.14  5105.7 1997.67  5113.5 2000.15  5141.8 2003.68  5147.0 2003.92
  5154.7 2005.41  5165.0 2006.03  5183.0 2007.77  5195.9 2007.74  5206.2 2008.26
#Mann=3,-1,0
  4900.1     0.1       0  4986.9    0.05       0  4993.2     0.1       0
Bank Sta=4986.9,4993.2
Exp/Cntr=0.3,0.1

Type RM Length L Ch R = 1,9127,483,483,483
BEGIN DESCRIPTION:
Stream0431 20.0
END DESCRIPTION:
XS GIS Cut Line= 3
      1885625.01     13967424.99      1885525.00     13967525.00
      1885525.00     13967724.97
#Sta/Elev= 30
  4858.7 2007.93  4862.2 2007.93  4887.0 2005.84  4915.3 2001.51  4929.4 1998.20
  4957.7 1990.35  4971.9 1985.34  4986.0 1985.89  4996.6 1984.80  5002.6 1984.80
  5006.9 1983.75  5007.4 1983.25  5012.8 1983.25  5013.3 1983.75  5020.1 1983.94
  5030.1 1987.49  5040.1 1989.68  5060.1 1991.43  5070.1 1991.39  5080.1 1991.82
  5090.1 1992.41  5100.1 1993.38  5120.1 1996.48  5130.1 1997.60  5140.1 1999.52
  5150.1 2001.87  5170.1 2005.05  5180.1 2005.72  5197.6 2007.81  5200.1 2007.81
#Mann=3,-1,0
  4858.7     0.1       0  5006.9    0.05       0  5013.3     0.1       0
Bank Sta=5006.9,5013.3
Exp/Cntr=0.3,0.1

Type RM Length L Ch R = 1,8644,444,444,444
BEGIN DESCRIPTION:
Stream0431 19.0
END DESCRIPTION:
XS GIS Cut Line= 3
      1885075.00     13967325.02      1885075.00     13967525.00
      1885075.00     13967675.02
#Sta/Elev= 30
  4795.5 2010.80  4805.5 2010.22  4815.5 2009.00  4825.5 2007.36  4845.5 2004.75
  4855.5 2002.51  4865.5 2000.77  4889.9 1997.54  4895.5 1996.80  4905.5 1996.06
  4915.5 1994.37  4935.5 1990.40  4945.5 1988.96  4965.5 1984.73  4985.5 1983.89
  4993.0 1982.84  4998.0 1982.84  5012.2 1980.93  5012.7 1980.43  5018.2 1980.43
  5018.7 1980.93  5035.5 1982.20  5065.5 1982.34  5075.5 1982.97  5085.5 1992.28
  5095.5 1997.22  5105.5 1998.30  5125.5 2003.40  5135.5 2005.20  5145.5 2005.95
#Mann=4,-1,0
  4795.5     0.1       0  4889.9    0.07       0  5012.2    0.05       0
  5018.7    0.07       0
Bank Sta=5012.2,5018.7
Exp/Cntr=0.3,0.1

Type RM Length L Ch R = 1,8200,445,445,445
BEGIN DESCRIPTION:
Stream0431 18.0
END DESCRIPTION:
XS GIS Cut Line= 3
      1884824.99     13967325.01      1884675.00     13967475.00
      1884575.02     13967574.98
#Sta/Elev= 30
  4792.5 1999.49  4796.0 1999.49  4820.8 1997.38  4849.0 1993.81  4863.2 1991.45
  4877.3 1989.38  4900.8 1983.01  4905.6 1981.76  4919.8 1979.49  4933.9 1976.80
  4948.0 1976.80  4954.5 1977.57  4962.2 1978.48  4976.3 1977.47  4987.2 1976.14
  4987.7 1975.64  4993.2 1975.64  4993.7 1976.14  5018.8 1976.76  5032.9 1977.49
  5047.0 1982.68  5061.2 1989.05  5075.3 1994.00  5089.5 1997.91  5103.6 2000.93
  5110.7 2004.94  5117.7 2006.12  5131.9 2009.53  5142.5 2010.88  5146.0 2010.88
#Mann=5,-1,0
  4792.5     0.1       0  4900.8    0.07       0  4954.5     0.1       0
  4987.2    0.05       0  4993.7     0.1       0
Bank Sta=4987.2,4993.7
Exp/Cntr=0.3,0.1

Type RM Length L Ch R = 1,7755,450,450,450
BEGIN DESCRIPTION:
Stream0431 17.0
END DESCRIPTION:
XS GIS Cut Line= 3
      1884325.00     13966775.01      1884375.00     13967175.00
      1884325.00     13967275.00
#Sta/Elev= 30
  4596.9 2038.67  4599.4 2038.67  4634.7 2029.70  4639.7 2029.99  4647.3 2028.17
  4687.6 2016.81  4697.7 2015.11  4707.7 2011.90  4715.3 2007.88  4720.3 2008.90
  4727.9 2005.06  4738.0 2002.85  4781.1 1988.61  4795.9 1983.43  4801.0 1985.10
  4808.5 1981.54  4818.6 1978.79  4838.8 1975.10  4858.9 1972.81  4880.6 1972.73
  4929.5 1971.65  4957.2 1968.89  4994.1 1968.64  4994.6 1968.14  5000.8 1968.64
  5030.7 1970.79  5036.3 1975.68  5053.1 1985.87  5058.7 1991.48  5111.8 2000.09
#Mann=6,-1,0
  4596.9    0.07       0  4599.4     0.1       0  4781.1    0.07       0
  4880.6     0.1       0  4994.1    0.05       0  5000.8     0.1       0
Bank Sta=4994.1,5000.8
Exp/Cntr=0.3,0.1

Type RM Length L Ch R = 1,7305,444,444,444
BEGIN DESCRIPTION:
Stream0431 16.0
END DESCRIPTION:
XS GIS Cut Line= 3
      1883974.99     13966924.97      1884025.00     13967025.00
      1884174.98     13967324.96
#Sta/Elev= 30
  4888.2 2012.22  4891.0 2012.22  4896.6 2009.24  4902.2 2008.44  4919.0 1999.48
  4924.6 1998.39  4933.0 1990.41  4941.3 1972.79  4955.3 1963.83  4963.7 1962.90
  4969.3 1963.44  4974.3 1962.03  4974.8 1961.53  4980.5 1961.53  4981.0 1962.03
  4991.6 1963.26  5002.8 1963.02  5014.0 1965.26  5022.4 1965.82  5036.4 1968.12
  5103.5 1973.76  5156.6 1977.03  5215.3 1986.37  5237.6 1988.29  5246.0 1990.02
  5254.4 1990.62  5268.4 1993.06  5282.3 1994.14  5313.1 1998.99  5335.4 2000.55
#Mann=3,-1,0
  4888.2     0.1       0  4974.3    0.05       0  4981.0     0.1       0
Bank Sta=4974.3,4981
Exp/Cntr=0.3,0.1

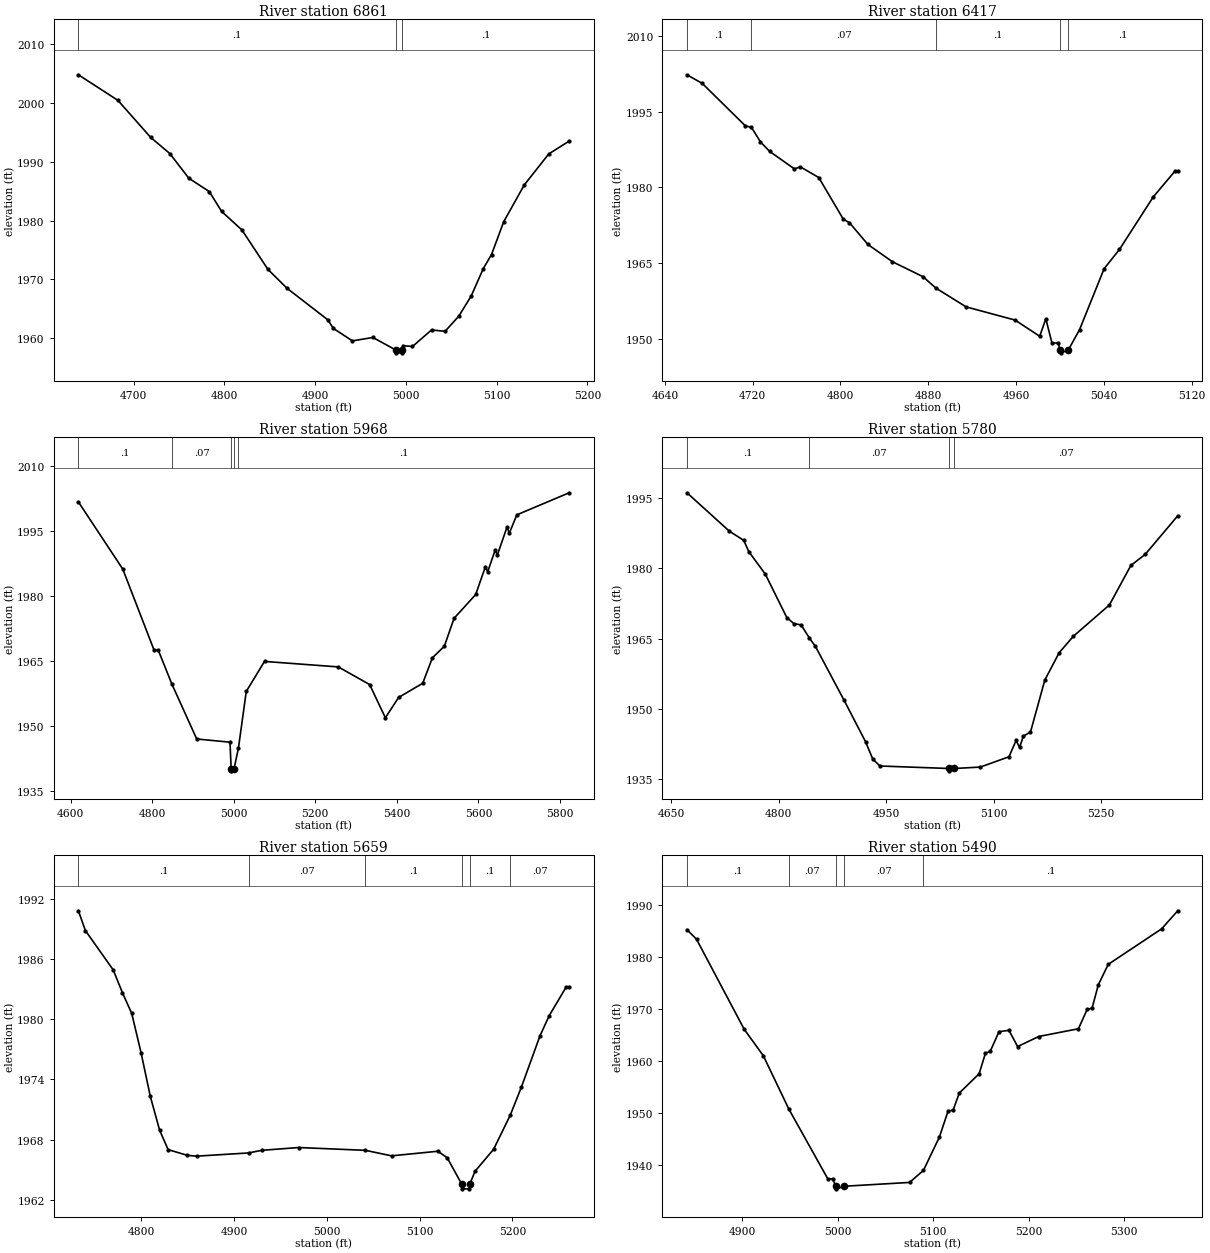
Type RM Length L Ch R = 1,6861,444,444,444
BEGIN DESCRIPTION:
Stream0431 15.0
END DESCRIPTION:
XS GIS Cut Line= 3
      1883424.99     13967124.99      1883725.00     13967325.00
      1883824.98     13967474.96
#Sta/Elev= 30
  4639.2 2004.75  4682.8 2000.40  4718.8 1994.12  4739.9 1991.38  4760.9 1987.18
  4783.4 1984.92  4797.0 1981.55  4819.5 1978.38  4848.0 1971.71  4869.1 1968.49
  4914.1 1963.13  4920.1 1961.68  4941.2 1959.56  4963.7 1960.14  4988.7 1958.03
  4989.2 1957.53  4995.4 1957.53  4995.9 1958.03  4996.8 1958.75  5007.3 1958.61
  5028.3 1961.41  5043.3 1961.19  5058.4 1963.77  5071.9 1967.15  5085.4 1971.85
  5094.4 1974.22  5107.9 1979.81  5130.5 1986.04  5157.5 1991.31  5180.0 1993.49
#Mann=3,-1,0
  4639.2     0.1       0  4988.7    0.05       0  4995.9     0.1       0
Bank Sta=4988.7,4995.9
Exp/Cntr=0.3,0.1

Type RM Length L Ch R = 1,6417,449,449,449
BEGIN DESCRIPTION:
Stream0431 14.0
END DESCRIPTION:
XS GIS Cut Line= 3
      1883225.02     13967275.04      1883375.00     13967575.00
      1883425.02     13967675.03
#Sta/Elev= 30
  4660.1 2002.36  4674.0 2000.65  4713.2 1992.25  4718.9 1991.90  4727.1 1989.03
  4735.5 1987.14  4757.9 1983.69  4763.5 1984.07  4780.2 1981.96  4802.6 1973.68
  4808.2 1972.99  4825.0 1968.67  4847.3 1965.25  4875.3 1962.26  4887.0 1960.00
  4914.4 1956.29  4959.1 1953.66  4981.5 1950.45  4987.1 1953.90  4992.7 1949.11
  4998.3 1949.11  5000.2 1947.66  5000.7 1947.16  5007.4 1947.66  5017.8 1951.75
  5040.2 1963.86  5054.2 1967.69  5084.9 1978.09  5104.5 1983.17  5107.3 1983.17
#Mann=5,-1,0
  4660.1     0.1       0  4718.9    0.07       0  4887.0     0.1       0
  5000.2    0.05       0  5007.4     0.1       0
Bank Sta=5000.2,5007.4
Exp/Cntr=0.3,0.1

Type RM Length L Ch R = 1,5968,188,188,188
BEGIN DESCRIPTION:
Stream0431 13.0
END DESCRIPTION:
XS GIS Cut Line= 4
      1882824.99     13967374.98      1882975.00     13967725.00
      1883025.00     13967825.00      1883298.39     13968481.00
#Sta/Elev= 30
  4619.2 2001.76  4728.0 1986.24  4804.2 1967.65  4815.1 1967.50  4848.4 1959.67
  4909.3 1946.99  4990.9 1946.25  4993.7 1940.13  4994.2 1939.63  5000.9 1940.13
  5011.7 1944.95  5030.8 1957.98  5075.5 1964.91  5256.4 1963.64  5333.3 1959.56
  5371.8 1951.89  5404.3 1956.59  5463.3 1959.85  5487.2 1965.75  5516.4 1968.41
  5540.2 1974.86  5593.3 1980.37  5617.1 1986.80  5622.6 1985.60  5641.0 1990.62
  5646.4 1989.49  5670.2 1995.99  5675.6 1994.49  5694.1 1998.77  5822.5 2003.87
#Mann=5,-1,0
  4619.2     0.1       0  4848.4    0.07       0  4993.7    0.05       0
  5000.9    0.07       0  5011.7     0.1       0
Bank Sta=4993.7,5000.9
Exp/Cntr=0.3,0.1

Type RM Length L Ch R = 1,5780,121,121,121
BEGIN DESCRIPTION:
Mapping XS e55d702e
END DESCRIPTION:
XS GIS Cut Line= 2
      1882787.65     13967425.75      1882805.87     13968110.41
#Sta/Elev= 30
  4672.1 1996.05  4731.4 1987.85  4751.4 1985.92  4758.4 1983.51  4781.4 1978.73
  4811.4 1969.48  4821.4 1968.17  4831.4 1967.91  4843.1 1965.07  4851.4 1963.32
  4891.4 1951.84  4921.4 1943.00  4931.4 1939.33  4941.4 1937.85  5037.8 1937.32
  5038.3 1936.82  5045.1 1937.32  5081.5 1937.62  5121.5 1939.82  5131.4 1943.29
  5136.3 1941.80  5141.5 1944.21  5151.5 1945.09  5171.5 1956.16  5191.5 1961.98
  5211.5 1965.51  5261.6 1972.15  5291.6 1980.57  5311.6 1982.93  5357.0 1991.15
#Mann=4,-1,0
  4672.1     0.1       0  4843.1    0.07       0  5037.8    0.05       0
  5045.1    0.07       0
Bank Sta=5037.8,5045.1
Exp/Cntr=0.3,0.1

Type RM Length L Ch R = 1,5659,169,169,169
BEGIN DESCRIPTION:
Mapping XS 0890a50c
END DESCRIPTION:
XS GIS Cut Line= 2
      1882678.85     13967507.48      1882684.87     13968036.45
#Sta/Elev= 30
  4732.3 1990.81  4739.8 1988.84  4769.8 1984.92  4779.8 1982.63  4789.8 1980.57
  4799.8 1976.67  4809.8 1972.31  4819.8 1968.94  4829.0 1966.99  4849.8 1966.42
  4859.8 1966.34  4915.7 1966.66  4929.8 1966.92  4969.8 1967.20  5041.7 1966.92
  5069.8 1966.37  5119.8 1966.83  5129.8 1966.18  5145.3 1963.58  5145.8 1963.08
  5153.8 1963.08  5154.3 1963.58  5159.8 1964.83  5179.8 1967.02  5197.7 1970.41
  5209.8 1973.23  5229.8 1978.33  5239.8 1980.36  5258.1 1983.21  5261.3 1983.21
#Mann=6,-1,0
  4732.3     0.1       0  4915.7    0.07       0  5041.7     0.1       0
  5145.3    0.05       0  5154.3     0.1       0  5197.7    0.07       0
Bank Sta=5145.3,5154.3
Exp/Cntr=0.3,0.1

Type RM Length L Ch R = 1,5490,431,431,431
BEGIN DESCRIPTION:
Stream0431 12.0
END DESCRIPTION:
XS GIS Cut Line= 3
      1882525.00     13967575.03      1882525.00     13967725.00
      1882625.01     13968075.03
#Sta/Elev= 30
  4842.0 1985.19  4852.0 1983.35  4902.0 1966.04  4922.0 1960.97  4948.6 1950.77
  4989.5 1937.34  4994.6 1937.34  4997.9 1935.92  4998.4 1935.42  5006.9 1935.92
  5075.2 1936.65  5089.7 1938.97  5106.4 1945.37  5115.5 1950.38  5120.7 1950.51
  5127.2 1953.81  5148.0 1957.52  5154.5 1961.41  5159.7 1961.87  5168.8 1965.59
  5179.2 1965.86  5188.3 1962.74  5210.4 1964.67  5252.0 1966.16  5261.1 1969.86
  5266.3 1970.12  5272.8 1974.60  5283.2 1978.52  5339.1 1985.34  5356.0 1988.81
#Mann=5,-1,0
  4842.0     0.1       0  4948.6    0.07       0  4997.9    0.05       0
  5006.9    0.07       0  5089.7     0.1       0
Bank Sta=4997.9,5006.9
Exp/Cntr=0.3,0.1

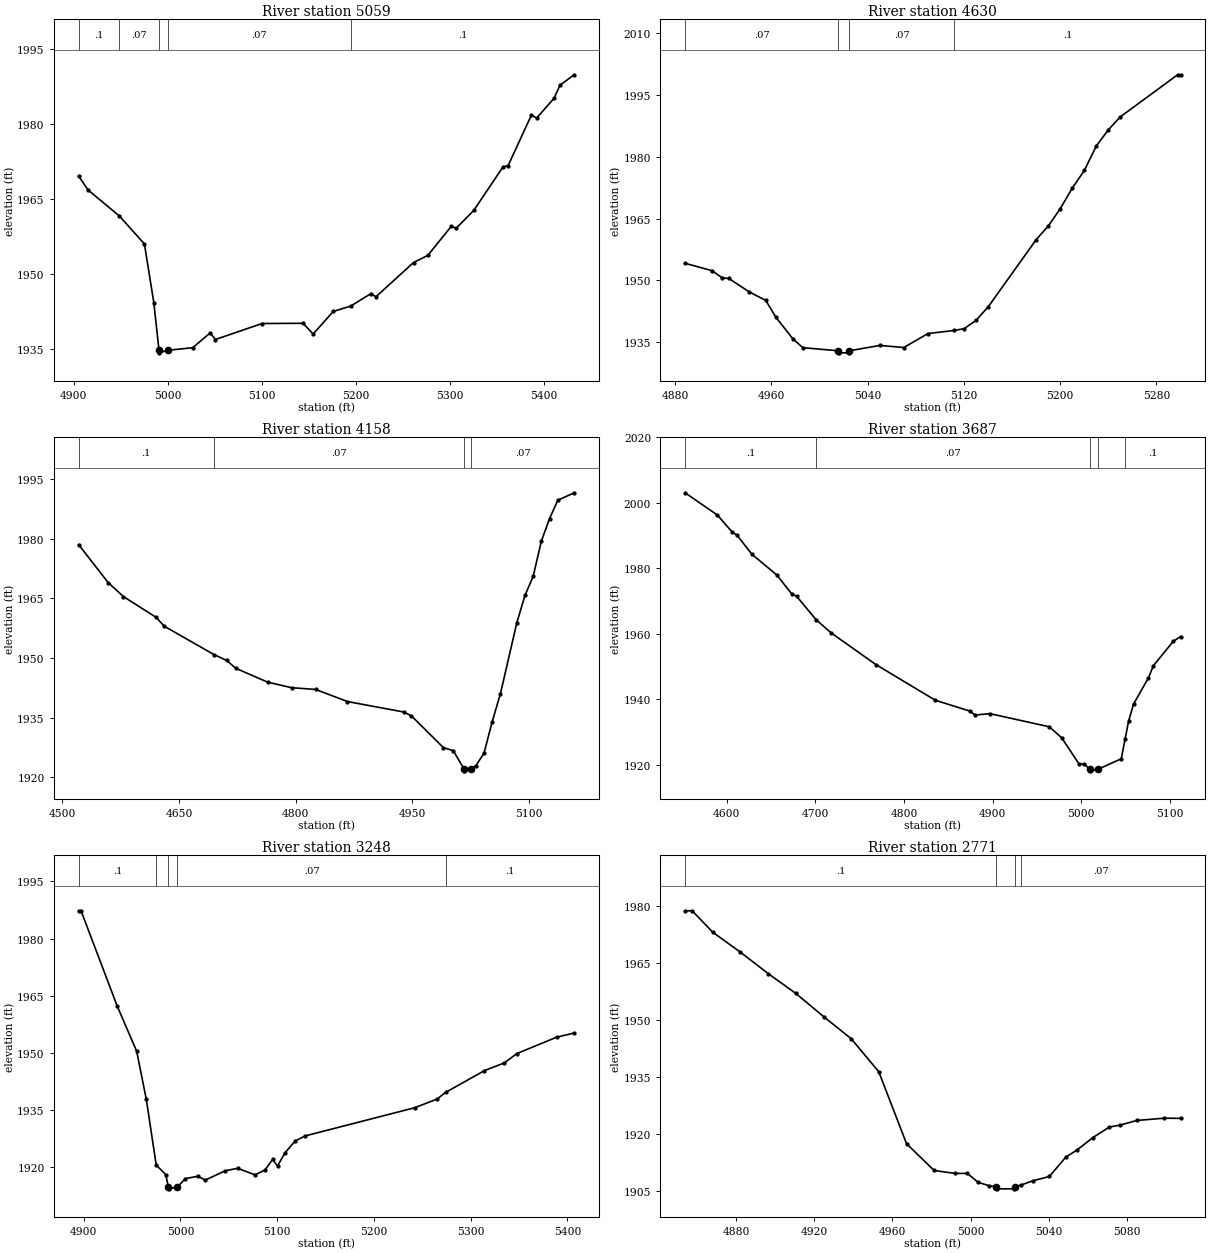
Type RM Length L Ch R = 1,5059,429,429,429
BEGIN DESCRIPTION:
Stream0431 11.0
END DESCRIPTION:
XS GIS Cut Line= 3
      1882175.00     13967675.00      1882175.00     13967775.00
      1882025.00     13968175.00
#Sta/Elev= 30
  4905.1 1969.64  4915.1 1966.86  4948.4 1961.67  4975.1 1956.07  4985.1 1944.33
  4990.6 1934.82  4991.1 1934.32  4999.7 1934.82  5026.5 1935.35  5045.2 1938.32
  5050.5 1936.98  5100.3 1940.18  5143.9 1940.22  5154.6 1938.07  5176.0 1942.59
  5194.5 1943.66  5216.0 1946.14  5221.4 1945.52  5261.4 1952.36  5276.6 1953.79
  5301.5 1959.58  5306.8 1959.21  5325.5 1962.78  5356.7 1971.49  5362.0 1971.71
  5386.9 1981.86  5392.3 1981.21  5410.9 1985.17  5417.2 1987.80  5432.3 1989.87
#Mann=5,-1,0
  4905.1     0.1       0  4948.4    0.07       0  4990.6    0.05       0
  4999.7    0.07       0  5194.5     0.1       0
Bank Sta=4990.6,4999.7
Exp/Cntr=0.3,0.1

Type RM Length L Ch R = 1,4630,472,472,472
BEGIN DESCRIPTION:
Stream0431 10.0
END DESCRIPTION:
XS GIS Cut Line= 3
      1881774.99     13967824.98      1881825.00     13967925.00
      1881825.00     13968224.98
#Sta/Elev= 30
  4888.3 1954.16  4910.7 1952.37  4919.1 1950.65  4924.7 1950.48  4941.4 1947.27
  4955.4 1945.15  4963.8 1941.07  4977.8 1935.89  4986.1 1933.72  5015.5 1932.97
  5016.0 1932.47  5024.3 1932.47  5024.8 1932.97  5050.1 1934.26  5070.1 1933.76
  5090.1 1937.14  5111.9 1937.89  5120.1 1938.32  5130.1 1940.34  5140.1 1943.58
  5180.1 1959.91  5190.1 1963.20  5200.1 1967.41  5210.1 1972.40  5220.1 1976.66
  5230.1 1982.62  5240.1 1986.53  5250.1 1989.67  5297.6 1999.83  5300.1 1999.83
#Mann=4,-1,0
  4888.3    0.07       0  5015.5    0.05       0  5024.8    0.07       0
  5111.9     0.1       0
Bank Sta=5015.5,5024.8
Exp/Cntr=0.3,0.1

Type RM Length L Ch R = 1,4158,471,471,471
BEGIN DESCRIPTION:
Stream0431 9.0
END DESCRIPTION:
XS GIS Cut Line= 3
      1881534.09     13967558.14      1881425.00     13968025.00
      1881374.99     13968175.04
#Sta/Elev= 30
  4520.9 1978.57  4558.8 1969.03  4578.5 1965.49  4620.4 1960.27  4631.3 1957.99
  4695.0 1950.87  4711.2 1949.42  4723.1 1947.41  4764.1 1943.92  4795.0 1942.52
  4825.8 1942.08  4866.8 1939.03  4939.1 1936.40  4949.0 1935.44  4990.1 1927.45
  5003.0 1926.63  5016.7 1922.07  5017.2 1921.57  5026.1 1922.07  5032.0 1922.86
  5042.5 1926.01  5053.0 1933.95  5063.6 1940.98  5084.7 1958.89  5095.2 1965.78
  5105.7 1970.56  5116.3 1979.46  5126.8 1985.13  5137.4 1989.75  5158.5 1991.64
#Mann=4,-1,0
  4520.9     0.1       0  4695.0    0.07       0  5016.7    0.05       0
  5026.1    0.07       0
Bank Sta=5016.7,5026.1
Exp/Cntr=0.3,0.1

Type RM Length L Ch R = 1,3687,439,439,439
BEGIN DESCRIPTION:
Stream0431 8.0
END DESCRIPTION:
XS GIS Cut Line= 3
      1881275.01     13967374.98      1881075.00     13967775.00
      1881025.02     13967874.96
#Sta/Elev= 30
  4553.0 2003.04  4589.4 1996.24  4606.1 1991.05  4611.7 1990.03  4628.5 1984.22
  4656.4 1977.94  4673.2 1972.18  4678.8 1971.43  4700.6 1964.31  4717.9 1960.21
  4768.2 1950.57  4835.3 1939.66  4874.5 1936.33  4880.1 1935.14  4896.8 1935.57
  4963.9 1931.55  4977.9 1928.16  4997.4 1920.18  5003.0 1920.18  5009.5 1918.60
  5010.0 1918.10  5018.9 1918.60  5045.0 1921.77  5049.4 1927.88  5053.3 1933.29
  5058.9 1938.51  5075.7 1946.51  5081.3 1950.24  5103.7 1957.66  5112.0 1959.13
#Mann=5,-1,0
  4553.0     0.1       0  4700.6    0.07       0  5009.5    0.05       0
  5018.9    0.07       0  5049.4     0.1       0
Bank Sta=5009.5,5018.9
Exp/Cntr=0.3,0.1

Type RM Length L Ch R = 1,3248,477,477,477
BEGIN DESCRIPTION:
Stream0431 7.0
END DESCRIPTION:
XS GIS Cut Line= 3
      1880775.00     13967375.03      1880775.00     13967475.00
      1880875.00     13967875.02
#Sta/Elev= 30
  4894.7 1987.29  4897.2 1987.29  4934.7 1962.20  4954.7 1950.42  4964.7 1937.76
  4974.9 1920.56  4984.7 1918.05  4987.5 1914.80  4988.0 1914.30  4996.9 1914.80
  5005.0 1916.98  5017.9 1917.61  5025.6 1916.59  5046.2 1919.04  5059.1 1919.69
  5077.1 1917.97  5087.4 1919.27  5095.2 1922.01  5100.3 1920.30  5108.1 1923.78
  5118.4 1926.82  5128.7 1928.18  5242.1 1935.59  5265.2 1937.86  5274.0 1939.60
  5314.2 1945.33  5334.8 1947.35  5347.7 1949.80  5388.9 1954.11  5407.0 1955.20
#Mann=5,-1,0
  4894.7     0.1       0  4974.9    0.07       0  4987.5    0.05       0
  4996.9    0.07       0  5274.0     0.1       0
Bank Sta=4987.5,4996.9
Exp/Cntr=0.3,0.1

Type RM Length L Ch R = 1,2771,444,444,444
BEGIN DESCRIPTION:
Stream0431 6.0
END DESCRIPTION:
XS GIS Cut Line= 3
      1880324.97     13967624.97      1880425.00     13967725.00
      1880525.03     13967775.01
#Sta/Elev= 30
  4854.0 1978.81  4857.6 1978.81  4868.2 1973.15  4882.3 1967.91  4896.5 1962.28
  4910.6 1957.08  4924.8 1950.98  4938.9 1945.17  4953.0 1936.48  4967.2 1917.55
  4981.3 1910.52  4991.9 1909.75  4998.3 1909.75  5003.8 1907.39  5009.4 1906.52
  5013.1 1906.19  5013.6 1905.69  5022.1 1905.69  5022.6 1906.19  5025.9 1906.73
  5031.8 1907.81  5040.2 1908.94  5048.6 1914.03  5054.2 1915.86  5062.5 1919.19
  5070.9 1921.94  5076.5 1922.47  5084.9 1923.67  5098.9 1924.27  5107.3 1924.22
#Mann=4,-1,0
  4854.0     0.1       0  5013.1    0.05       0  5022.6     0.1       0
  5025.9    0.07       0
Bank Sta=5013.1,5022.6
Exp/Cntr=0.3,0.1

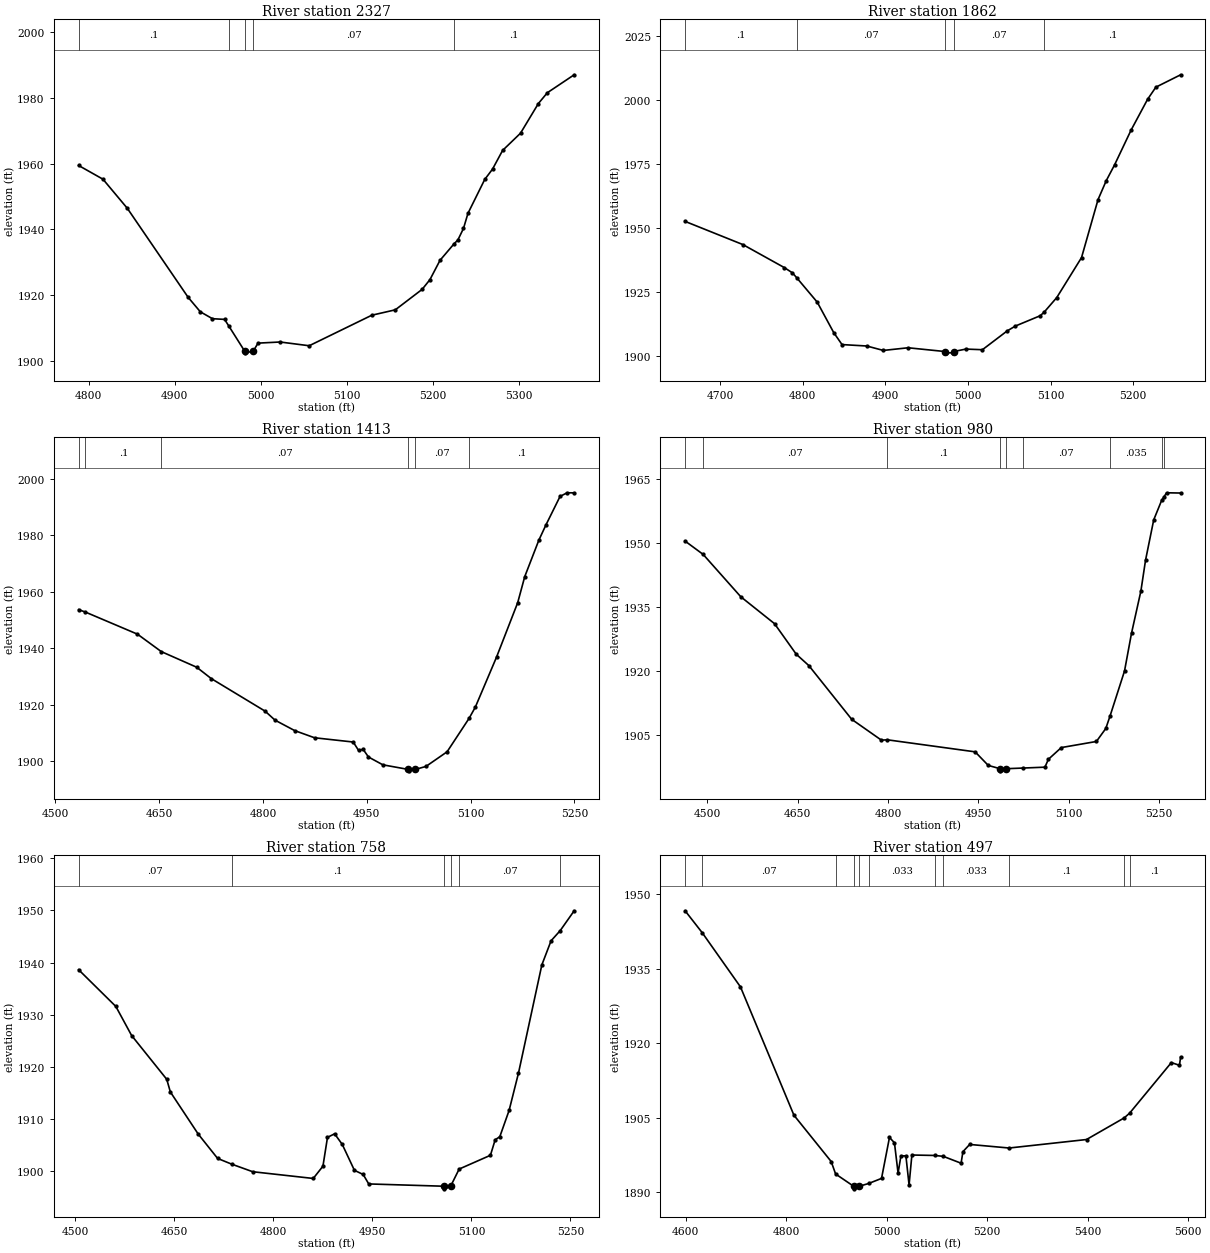
Type RM Length L Ch R = 1,2327,465,465,465
BEGIN DESCRIPTION:
Stream0431 5.0
END DESCRIPTION:
XS GIS Cut Line= 3
      1880024.97     13967924.97      1880175.00     13968075.00
      1880275.01     13968425.03
#Sta/Elev= 30
  4788.1 1959.46  4816.4 1955.28  4844.7 1946.42  4915.4 1919.31  4929.6 1914.89
  4943.7 1912.79  4957.8 1912.58  4962.7 1910.57  4981.2 1902.89  4981.7 1902.39
  4991.1 1902.89  4996.7 1905.35  5022.4 1905.69  5056.2 1904.55  5129.0 1913.85
  5156.3 1915.49  5187.5 1921.72  5196.6 1924.69  5208.3 1930.57  5224.3 1935.50
  5229.1 1936.79  5235.6 1940.28  5240.8 1944.88  5260.3 1955.20  5269.4 1958.37
  5281.1 1964.05  5301.9 1969.29  5322.7 1978.34  5333.1 1981.62  5364.3 1987.09
#Mann=5,-1,0
  4788.1     0.1       0  4962.7    0.07       0  4981.2    0.05       0
  4991.1    0.07       0  5224.3     0.1       0
Bank Sta=4981.2,4991.1
Exp/Cntr=0.3,0.1

Type RM Length L Ch R = 1,1862,449,449,449
BEGIN DESCRIPTION:
Stream0431 4.0
END DESCRIPTION:
XS GIS Cut Line= 3
      1879875.00     13968024.96      1879875.00     13968375.00
      1879875.00     13968624.96
#Sta/Elev= 30
  4657.5 1952.50  4727.5 1943.44  4777.5 1934.48  4787.5 1932.39  4792.6 1930.50
  4817.5 1920.95  4837.5 1909.03  4847.5 1904.38  4877.5 1903.82  4897.5 1902.09
  4927.5 1903.13  4972.5 1901.65  4973.0 1901.15  4982.0 1901.15  4982.5 1901.65
  4997.5 1902.62  5017.5 1902.37  5047.5 1909.72  5057.5 1911.63  5087.5 1915.65
  5092.3 1917.07  5107.5 1922.74  5137.5 1938.36  5157.5 1961.03  5167.5 1968.46
  5177.5 1974.58  5197.5 1988.17  5217.5 2000.21  5227.5 2004.94  5257.5 2009.78
#Mann=5,-1,0
  4657.5     0.1       0  4792.6    0.07       0  4972.5    0.05       0
  4982.5    0.07       0  5092.3     0.1       0
Bank Sta=4972.5,4982.5
Exp/Cntr=0.3,0.1

Type RM Length L Ch R = 1,1413,433,433,433
BEGIN DESCRIPTION:
Stream0431 3.0
END DESCRIPTION:
XS GIS Cut Line= 3
      1879774.98     13967975.03      1879475.00     13968325.00
      1879425.00     13968575.01
#Sta/Elev= 30
  4533.7 1953.73  4543.4 1952.88  4618.7 1945.05  4653.1 1938.88  4704.3 1933.34
  4725.2 1929.34  4803.1 1917.79  4817.4 1914.61  4845.9 1910.90  4874.5 1908.37
  4930.4 1906.86  4938.1 1903.90  4944.7 1904.29  4952.4 1901.56  4973.2 1898.79
  5010.0 1897.16  5010.5 1896.66  5020.0 1897.16  5035.4 1898.21  5066.0 1903.40
  5097.8 1915.25  5106.8 1919.22  5137.4 1936.90  5168.0 1956.19  5178.2 1965.43
  5198.6 1978.35  5208.8 1983.72  5229.2 1993.82  5239.4 1995.11  5249.6 1995.08
#Mann=6,-1,0
  4533.7    0.07       0  4543.4     0.1       0  4653.1    0.07       0
  5010.0    0.05       0  5020.0    0.07       0  5097.8     0.1       0
Bank Sta=5010,5020
Exp/Cntr=0.3,0.1

Type RM Length L Ch R = 1,980,222,222,222
BEGIN DESCRIPTION:
Stream0431 2.0
END DESCRIPTION:
XS GIS Cut Line= 3
      1879574.99     13967775.01      1879175.00     13968125.00
      1878925.04     13968274.98
#Sta/Elev= 30
  4462.8 1950.43  4492.8 1947.31  4555.3 1937.39  4611.3 1931.09  4647.4 1923.93
  4668.3 1921.27  4739.5 1908.68  4788.8 1903.80  4798.7 1903.88  4944.5 1901.06
  4966.3 1897.88  4985.9 1897.11  4986.4 1896.61  4996.0 1897.11  5023.4 1897.26
  5060.4 1897.47  5066.2 1899.32  5087.6 1902.06  5145.9 1903.49  5161.5 1906.53
  5168.6 1909.47  5192.6 1920.00  5204.2 1928.84  5219.8 1938.74  5227.5 1945.95
  5241.1 1955.41  5254.2 1959.95  5257.9 1960.75  5262.5 1961.75  5285.8 1961.69
#Mann=9,-1,0
  4462.8     0.1       0  4492.8    0.07       0  4798.7     0.1       0
  4985.9    0.05       0  4996.0     0.1       0  5023.4    0.07       0
  5168.6   0.035       0  5254.2     0.1       0  5257.9   0.035       0
Bank Sta=4985.9,4996
Exp/Cntr=0.3,0.1

Type RM Length L Ch R = 1,758,261,261,261
BEGIN DESCRIPTION:
Stream0431 T
END DESCRIPTION:
XS GIS Cut Line= 4
      1879493.44     13967799.00      1879084.57     13967968.28
      1878962.18     13967991.72      1878829.67     13968119.03
#Sta/Elev= 30
  4504.8 1938.64  4561.2 1931.60  4585.1 1926.03  4638.3 1917.64  4643.8 1915.21
  4686.0 1907.14  4715.4 1902.47  4736.6 1901.38  4768.6 1899.92  4860.3 1898.63
  4875.0 1900.98  4881.9 1906.51  4892.7 1907.19  4904.3 1905.15  4922.7 1900.19
  4936.0 1899.39  4944.4 1897.58  5058.3 1897.14  5058.8 1896.64  5068.5 1897.14
  5081.4 1900.43  5128.8 1903.07  5136.0 1906.05  5143.0 1906.63  5157.1 1911.67
  5171.3 1918.82  5206.7 1939.56  5220.7 1944.19  5234.5 1946.13  5255.7 1949.94
#Mann=6,-1,0
  4504.8    0.07       0  4736.6     0.1       0  5058.3    0.05       0
  5068.5     0.1       0  5081.4    0.07       0  5234.5   0.035       0
Bank Sta=5058.3,5068.5
Exp/Cntr=0.3,0.1

Type RM Length L Ch R = 1,497,272,272,272
BEGIN DESCRIPTION:
Stream0431 1.0
END DESCRIPTION:
XS GIS Cut Line= 5
      1879524.98     13967725.00      1879118.54     13967753.08
      1879048.18     13967623.54      1879021.54     13967616.88
      1878667.37     13967810.87
#Sta/Elev= 30
  4598.8 1946.68  4632.9 1942.26  4709.0 1931.35  4815.4 1905.51  4889.5 1896.19
  4898.3 1893.68  4934.5 1891.19  4935.0 1890.69  4944.7 1891.19  4964.1 1891.77
  4989.7 1892.79  5005.5 1901.04  5015.4 1899.96  5022.6 1893.87  5028.3 1897.32
  5038.2 1897.33  5044.5 1891.47  5050.1 1897.50  5096.2 1897.41  5112.6 1897.23
  5148.0 1895.85  5151.7 1898.18  5165.1 1899.63  5243.6 1898.91  5397.6 1900.62
  5472.5 1904.97  5483.4 1905.93  5566.4 1916.11  5582.5 1915.57  5584.9 1917.24
#Mann=11,-1,0
  4598.8     0.1       0  4632.9    0.07       0  4898.3     0.1       0
  4934.5   0.033       0  4944.7     0.1       0  4964.1   0.033       0
  5096.2    0.07       0  5112.6   0.033       0  5243.6     0.1       0
  5472.5    0.07       0  5483.4     0.1       0
Bank Sta=4934.5,4944.7
Exp/Cntr=0.3,0.1

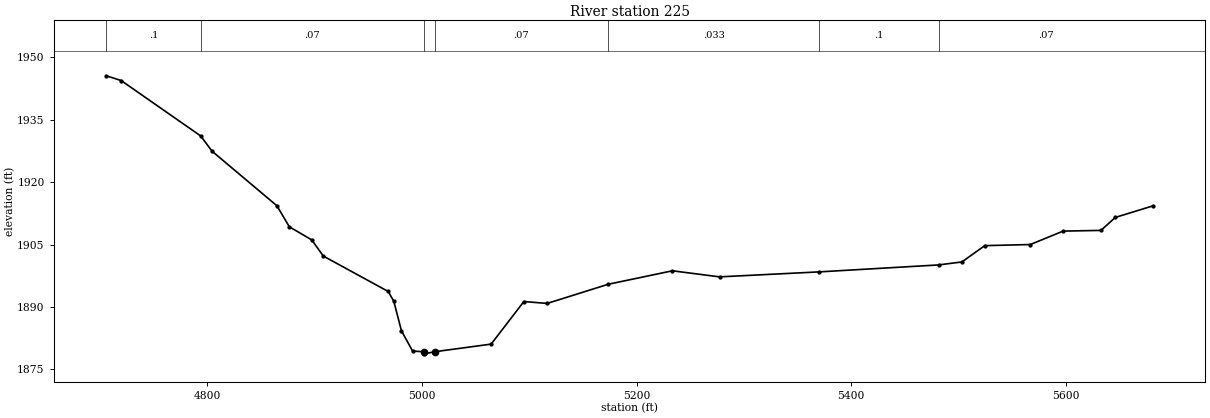
Type RM Length L Ch R = 1,225,0,0,0
BEGIN DESCRIPTION:
Stream0431 0.0
END DESCRIPTION:
XS GIS Cut Line= 4
      1879548.27     13967617.53      1879171.64     13967502.90
      1879058.75     13967537.02      1878663.66     13967780.66
#Sta/Elev= 30
  4705.7 1945.60  4719.6 1944.46  4793.8 1931.12  4804.3 1927.47  4864.8 1914.33
  4876.4 1909.27  4897.3 1906.11  4908.1 1902.22  4968.6 1893.70  4973.8 1891.33
  4980.9 1884.24  4991.3 1879.37  5001.6 1879.20  5002.1 1878.70  5011.8 1879.20
  5064.5 1881.04  5095.0 1891.28  5116.8 1890.83  5173.5 1895.43  5233.5 1898.68
  5277.4 1897.22  5370.4 1898.42  5481.5 1900.09  5503.3 1900.81  5524.6 1904.73
  5567.1 1905.00  5597.7 1908.23  5632.9 1908.40  5646.3 1911.52  5681.5 1914.31
#Mann=7,-1,0
  4705.7     0.1       0  4793.8    0.07       0  5001.6    0.05       0
  5011.8    0.07       0  5173.5   0.033       0  5370.4     0.1       0
  5481.5    0.07       0
Bank Sta=5001.6,5011.8
Exp/Cntr=0.3,0.1

Chan Stop Cuts=-1