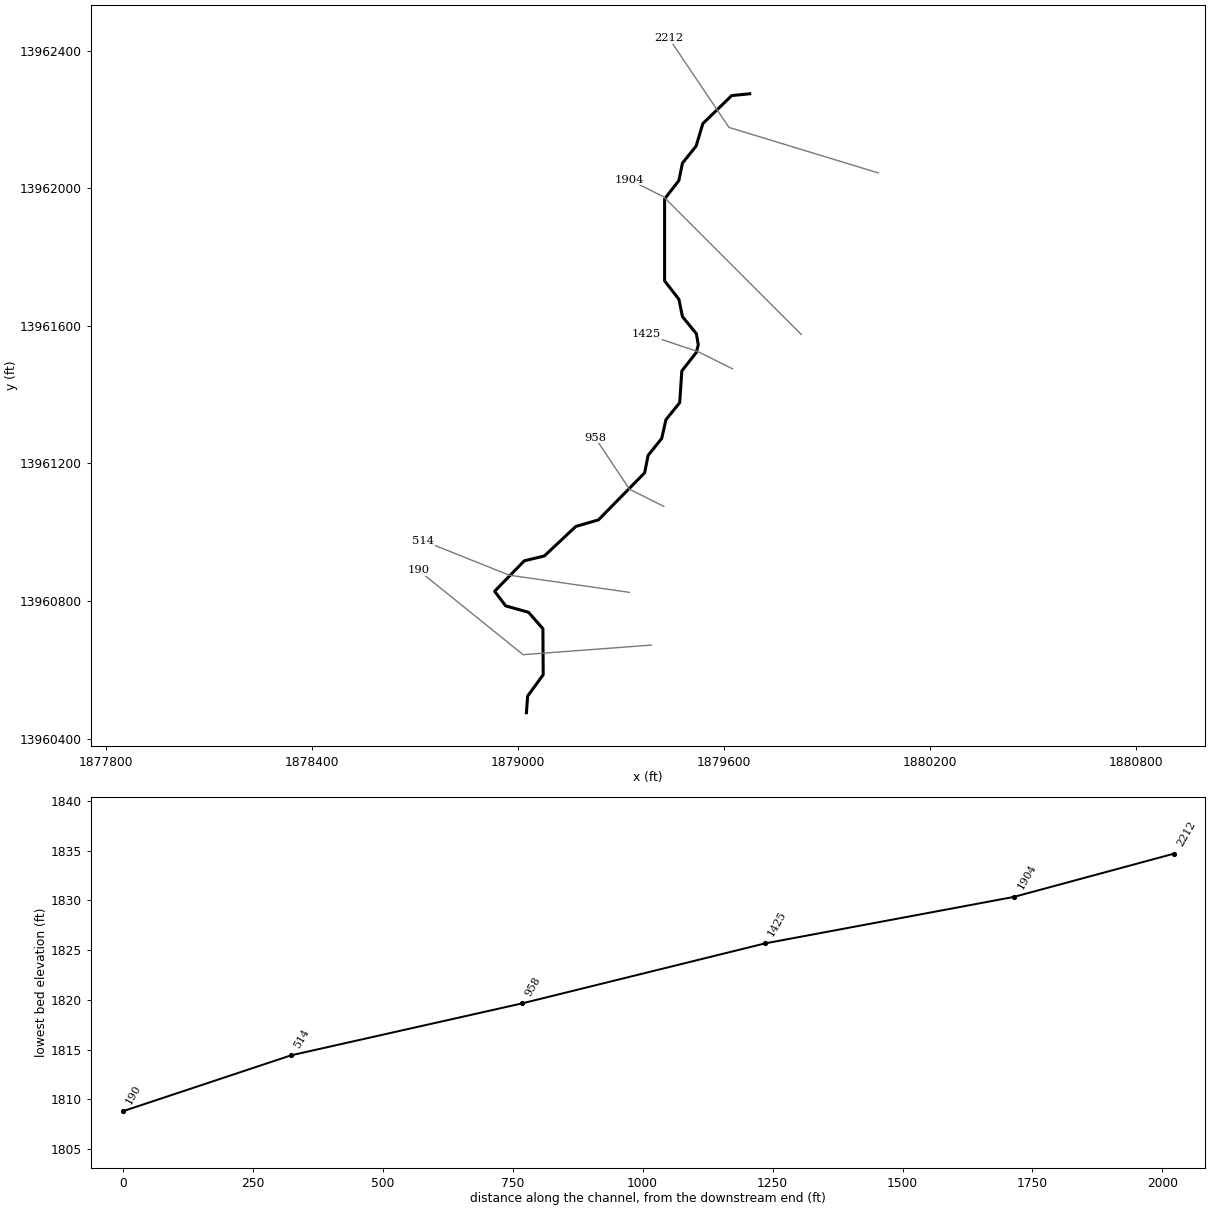
--- Stream0432.prj (project) ---

Proj Title=Stream0432 Base Level Engineering
Current Plan=p01
Default Exp/Contr=0.3,0.1
English Units
Geom File=g01
Flow File=f01
Plan File=p01
BEGIN DESCRIPTION:
Stream0432
END DESCRIPTION:

--- Stream0432.p01 (plan) ---

Plan Title=Multiple Run
Short Identifier=Multiple
Geom File=g01
Flow File=f01
Subcritical Flow
K Sum by GR= 0
Std Step Tol= 0.01
Critical Tol= 0.01
Num of Std Step Trials= 20
Max Error Tol= 0.3
Flow Tol Ratio= 0.001
Split Flow NTrial= 30
Split Flow Tol= 0.02
Split Flow Ratio= 0.02
Log Output Level= 0
Friction Slope Method= 1
Unsteady Friction Slope Method= 2
Unsteady Bridges Friction Slope Method= 1
Parabolic Critical Depth
Global Vel Dist=  1 , 1 , 1
Global Log Level= 0
CheckData=True
Encroach Param= -1, 0, 0, 0
BEGIN DESCRIPTION:
Multiple Run
END DESCRIPTION:

--- Stream0432.f01 (steady flow) ---

Flow Title=Multiple
Number of Profiles=7
Profile Names=10-year,25-year,50-year,1pct_min,100-year,1pct_plu,500-year
River Rch & RM= Stream0432,Reach-1,2212
    1524    2657    3757    2567    5121   10218    9403
Boundary for River Rch & Prof#=Stream0432,Reach-1,1
Up Type=0
Dn Type=3
Dn Slope=0.005
Boundary for River Rch & Prof#=Stream0432,Reach-1,2
Up Type=0
Dn Type=3
Dn Slope=0.005
Boundary for River Rch & Prof#=Stream0432,Reach-1,3
Up Type=0
Dn Type=3
Dn Slope=0.005
Boundary for River Rch & Prof#=Stream0432,Reach-1,4
Up Type=0
Dn Type=3
Dn Slope=0.005
Boundary for River Rch & Prof#=Stream0432,Reach-1,5
Up Type=0
Dn Type=3
Dn Slope=0.005
Boundary for River Rch & Prof#=Stream0432,Reach-1,6
Up Type=0
Dn Type=3
Dn Slope=0.005
Boundary for River Rch & Prof#=Stream0432,Reach-1,7
Up Type=0
Dn Type=3
Dn Slope=0.005

--- Stream0432.g01 (geometry) ---

Geom Title=Existing Conditions

River Reach=Stream0432,Reach-1
Reach XY= 30
      1879675.00     13962275.00      1879622.46     13962269.70
      1879538.60     13962188.24      1879518.90     13962122.81
      1879479.16     13962073.28      1879468.88     13962022.82
      1879427.24     13961969.07      1879427.24     13961730.93
      1879468.89     13961677.18      1879479.22     13961626.72
      1879519.66     13961577.20      1879525.29     13961545.18
      1879519.63     13961522.82      1879477.38     13961469.03
      1879471.17     13961376.58      1879431.12     13961327.18
      1879418.92     13961272.80      1879379.19     13961223.26
      1879369.17     13961172.70      1879234.68     13961035.78
      1879168.96     13961016.82      1879077.28     13960930.87
      1879018.91     13960916.84      1878932.51     13960828.17
      1878964.58     13960785.79      1879031.34     13960766.98
      1879073.03     13960719.32      1879073.90     13960585.47
      1879028.65     13960523.49      1879025.00     13960475.00

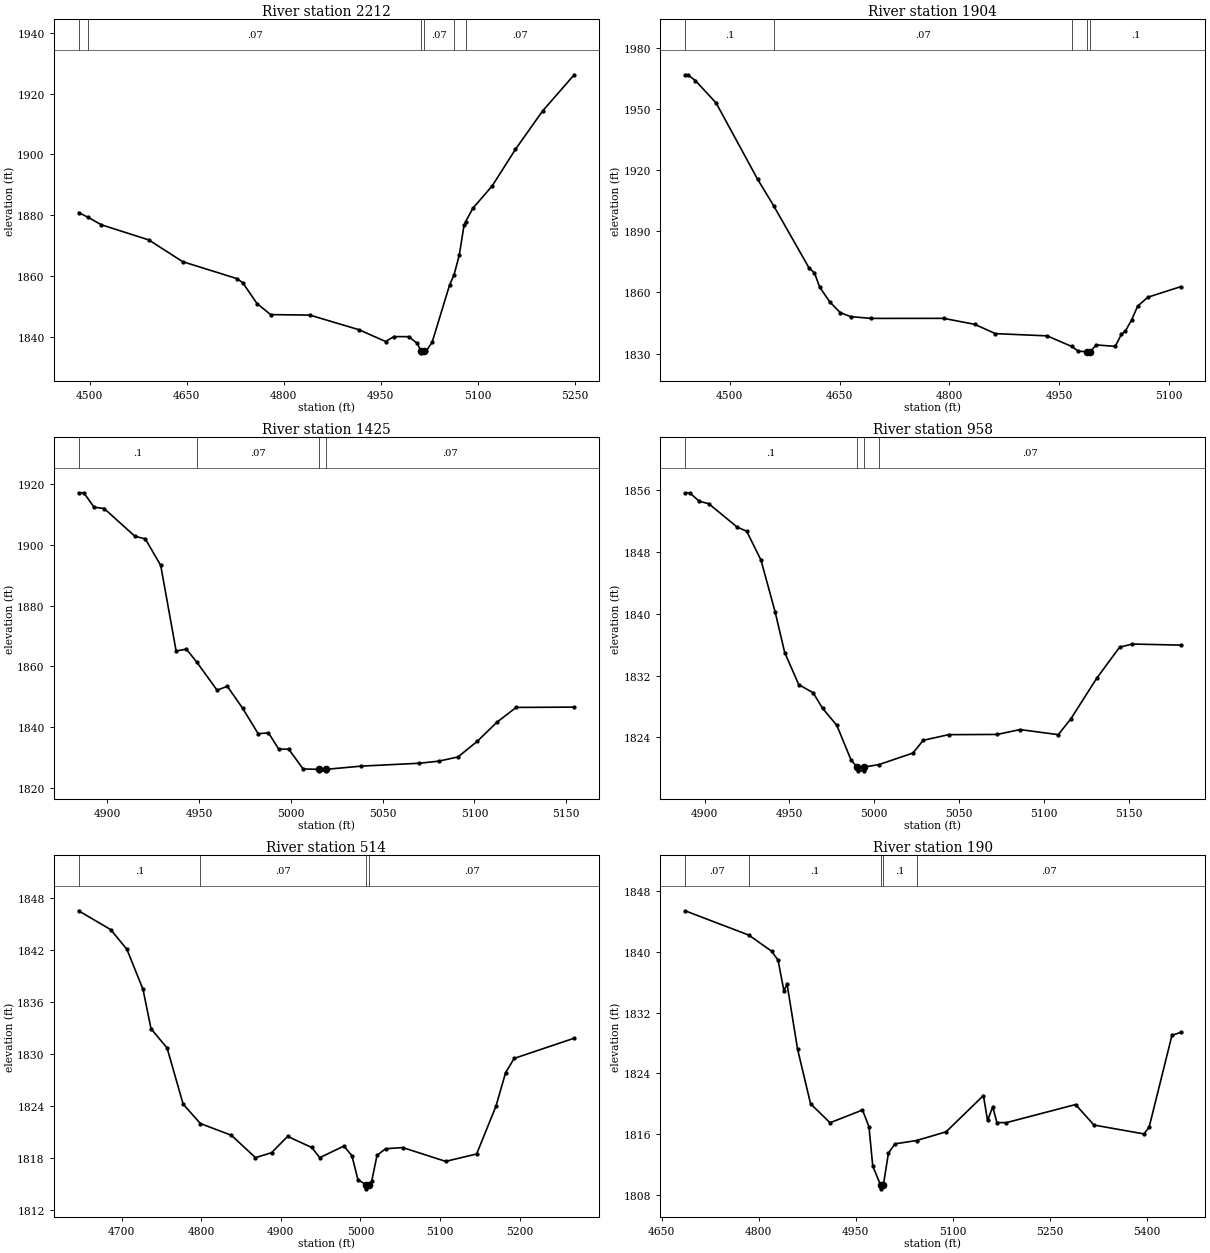
Type RM Length L Ch R = 1,2212,308,308,308
BEGIN DESCRIPTION:
Stream0432 5.0
END DESCRIPTION:
XS GIS Cut Line= 3
      1880048.81     13962044.92      1879614.62     13962177.12
      1879439.95     13962436.29
#Sta/Elev= 30
  4482.7 1880.85  4497.6 1879.25  4518.0 1876.81  4591.2 1871.85  4643.5 1864.70
  4727.1 1859.15  4736.4 1857.80  4758.5 1850.93  4779.7 1847.27  4840.2 1847.12
  4916.3 1842.30  4957.4 1838.43  4970.2 1840.04  4993.4 1840.02  5006.4 1837.80
  5012.4 1835.20  5012.7 1834.70  5016.5 1835.20  5020.4 1835.36  5029.4 1838.16
  5056.4 1856.99  5063.3 1860.37  5071.4 1866.84  5078.7 1876.60  5081.2 1877.84
  5092.4 1882.26  5122.3 1889.61  5158.3 1901.65  5200.3 1914.27  5249.1 1926.17
#Mann=6,-1,0
  4482.7     0.1       0  4497.6    0.07       0  5012.4    0.05       0
  5016.5    0.07       0  5063.3     0.1       0  5081.2    0.07       0
Bank Sta=5012.4,5016.5
Exp/Cntr=0.3,0.1

Type RM Length L Ch R = 1,1904,479,479,479
BEGIN DESCRIPTION:
Stream0432 4.0
END DESCRIPTION:
XS GIS Cut Line= 3
      1879825.01     13961574.99      1879425.00     13961975.00
      1879325.01     13962025.00
#Sta/Elev= 30
  4438.8 1966.95  4442.4 1966.95  4453.0 1964.06  4481.2 1953.11  4537.8 1915.71
  4559.8 1902.66  4608.5 1871.90  4615.6 1869.72  4622.7 1862.69  4636.8 1855.27
  4651.0 1850.11  4665.1 1848.14  4693.4 1847.27  4792.4 1847.29  4834.8 1844.34
  4863.1 1839.79  4933.8 1838.69  4967.4 1833.48  4976.2 1831.20  4988.3 1830.85
  4988.6 1830.35  4992.4 1830.85  5001.0 1834.24  5026.9 1833.53  5035.3 1839.40
  5040.8 1841.10  5049.2 1846.46  5057.6 1853.34  5071.6 1857.69  5116.3 1862.85
#Mann=5,-1,0
  4438.8     0.1       0  4559.8    0.07       0  4967.4     0.1       0
  4988.3    0.05       0  4992.4     0.1       0
Bank Sta=4988.3,4992.4
Exp/Cntr=0.3,0.1

Type RM Length L Ch R = 1,1425,467,467,467
BEGIN DESCRIPTION:
Stream0432 3.0
END DESCRIPTION:
XS GIS Cut Line= 3
      1879624.97     13961475.02      1879525.00     13961525.00
      1879374.98     13961575.01
#Sta/Elev= 30
  4884.4 1917.09  4887.2 1917.09  4892.8 1912.35  4898.3 1911.92  4915.1 1902.77
  4920.7 1901.94  4929.1 1893.23  4937.5 1865.08  4943.1 1865.67  4948.7 1861.46
  4959.8 1852.20  4965.4 1853.46  4973.8 1846.17  4982.2 1837.88  4987.8 1838.15
  4993.4 1832.80  4998.8 1832.80  5006.7 1826.28  5015.2 1826.17  5015.5 1825.67
  5019.1 1825.67  5019.3 1826.17  5038.3 1827.22  5070.0 1828.17  5080.5 1828.85
  5091.0 1830.23  5101.6 1835.42  5112.1 1841.59  5122.7 1846.52  5154.3 1846.62
#Mann=4,-1,0
  4884.4     0.1       0  4948.7    0.07       0  5015.2    0.05       0
  5019.3    0.07       0
Bank Sta=5015.2,5019.3
Exp/Cntr=0.3,0.1

Type RM Length L Ch R = 1,958,444,444,444
BEGIN DESCRIPTION:
Stream0432 2.0
END DESCRIPTION:
XS GIS Cut Line= 3
      1879424.96     13961075.02      1879325.00     13961125.00
      1879225.02     13961274.97
#Sta/Elev= 30
  4888.5 1855.69  4891.2 1855.69  4896.8 1854.59  4902.4 1854.28  4919.2 1851.24
  4924.8 1850.70  4933.2 1846.97  4941.6 1840.20  4947.2 1834.97  4955.5 1830.81
  4963.9 1829.77  4969.5 1827.75  4977.9 1825.54  4986.3 1821.04  4989.8 1820.14
  4990.1 1819.64  4993.7 1819.64  4993.9 1820.14  5002.6 1820.44  5022.8 1821.95
  5028.8 1823.60  5043.8 1824.33  5072.4 1824.36  5085.9 1824.99  5108.4 1824.33
  5115.9 1826.41  5131.0 1831.63  5144.5 1835.66  5152.0 1836.08  5180.5 1835.94
#Mann=4,-1,0
  4888.5     0.1       0  4989.8    0.05       0  4993.9     0.1       0
  5002.6    0.07       0
Bank Sta=4989.8,4993.9
Exp/Cntr=0.3,0.1

Type RM Length L Ch R = 1,514,324,324,324
BEGIN DESCRIPTION:
Stream0432 1.0
END DESCRIPTION:
XS GIS Cut Line= 3
      1879325.04     13960824.99      1878975.00     13960875.00
      1878724.96     13960975.02
#Sta/Elev= 30
  4645.8 1846.50  4686.2 1844.32  4706.5 1842.05  4726.7 1837.44  4736.8 1832.89
  4757.0 1830.67  4777.2 1824.19  4798.9 1821.95  4837.8 1820.60  4868.1 1818.02
  4888.3 1818.59  4908.5 1820.47  4938.8 1819.19  4948.9 1818.02  4979.2 1819.35
  4989.3 1818.25  4996.9 1815.46  5006.7 1814.92  5007.0 1814.42  5011.0 1814.92
  5014.2 1815.32  5020.9 1818.29  5031.7 1819.05  5053.2 1819.18  5107.1 1817.59
  5146.1 1818.44  5170.4 1823.96  5182.5 1827.82  5193.3 1829.47  5268.7 1831.80
#Mann=4,-1,0
  4645.8     0.1       0  4798.9    0.07       0  5006.7    0.05       0
  5011.0    0.07       0
Bank Sta=5006.7,5011
Exp/Cntr=0.3,0.1

Type RM Length L Ch R = 1,190,0,0,0
BEGIN DESCRIPTION:
Stream0432 0.0
END DESCRIPTION:
XS GIS Cut Line= 3
      1879388.15     13960671.67      1879015.41     13960643.78
      1878710.73     13960889.35
#Sta/Elev= 30
  4686.4 1845.40  4785.0 1842.19  4819.9 1840.08  4829.9 1838.91  4838.9 1834.90
  4843.9 1835.71  4860.0 1827.20  4880.1 1819.99  4910.2 1817.49  4960.3 1819.17
  4970.3 1816.97  4976.1 1811.80  4988.2 1809.29  4988.5 1808.79  4992.5 1809.29
  5000.4 1813.51  5010.4 1814.71  5043.7 1815.15  5089.4 1816.30  5147.0 1821.07
  5153.4 1817.79  5161.4 1819.59  5167.8 1817.52  5182.2 1817.50  5289.3 1819.89
  5317.6 1817.19  5394.9 1816.02  5402.9 1816.93  5438.1 1829.00  5451.5 1829.39
#Mann=5,-1,0
  4686.4    0.07       0  4785.0     0.1       0  4988.2    0.05       0
  4992.5     0.1       0  5043.7    0.07       0
Bank Sta=4988.2,4992.5
Exp/Cntr=0.3,0.1

Chan Stop Cuts=-1