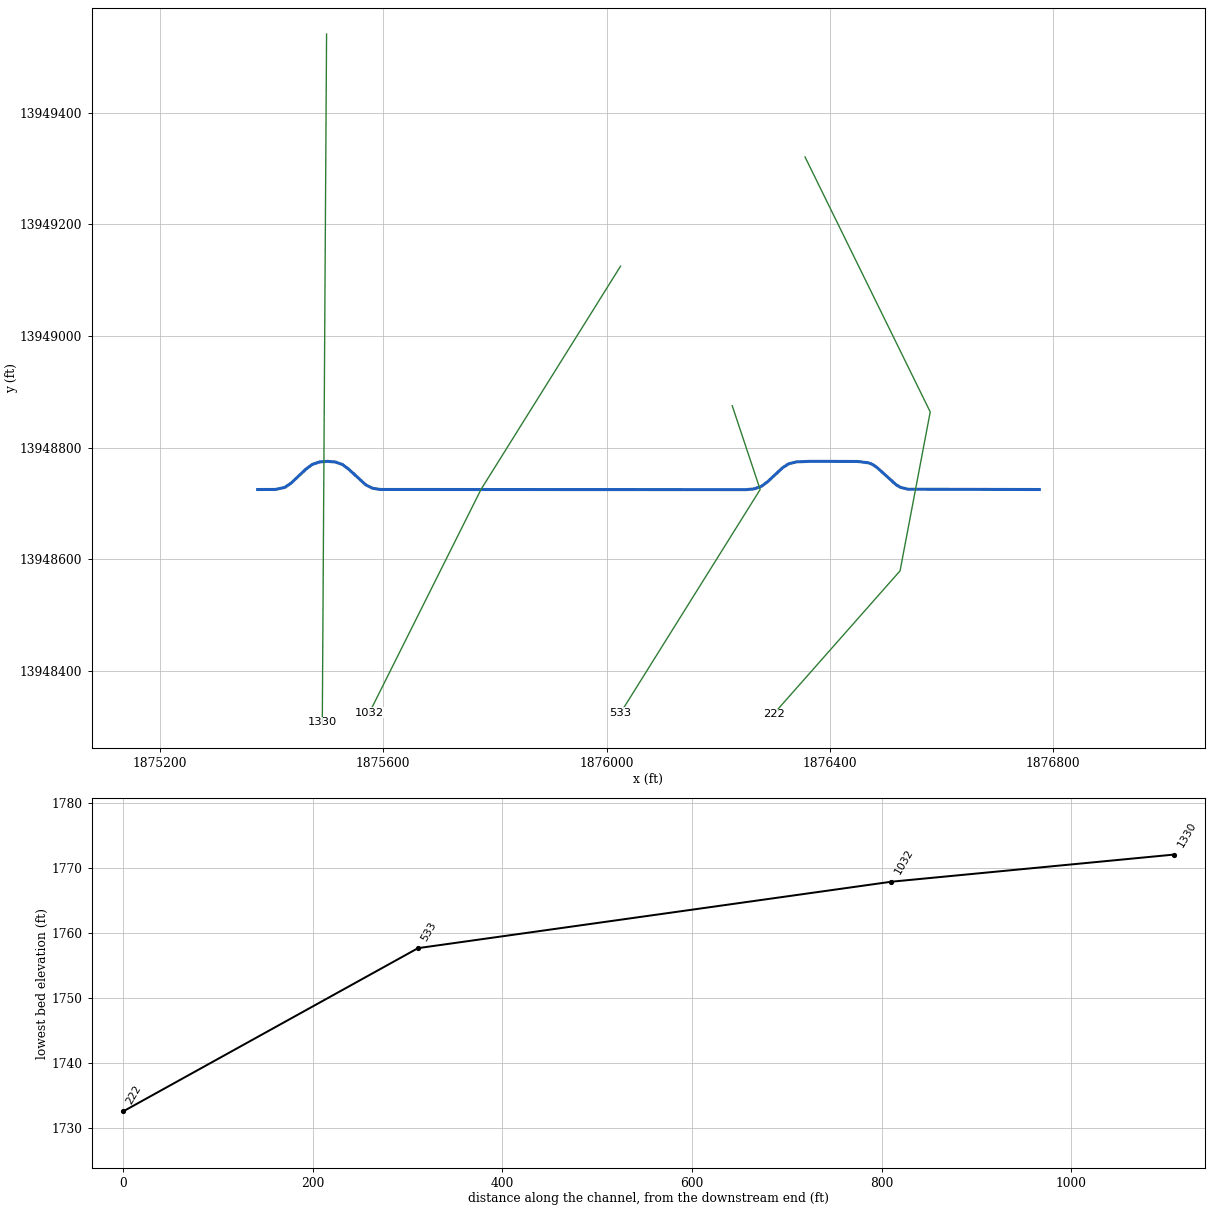
--- Stream0436.prj (project) ---

Proj Title=Stream0436 Base Level Engineering
Current Plan=p01
Default Exp/Contr=0.3,0.1
English Units
Geom File=g01
Flow File=f01
Plan File=p01
BEGIN DESCRIPTION:
Stream0436
END DESCRIPTION:

--- Stream0436.p01 (plan) ---

Plan Title=Multiple Run
Short Identifier=Multiple
Geom File=g01
Flow File=f01
Subcritical Flow
K Sum by GR= 0
Std Step Tol= 0.01
Critical Tol= 0.01
Num of Std Step Trials= 20
Max Error Tol= 0.3
Flow Tol Ratio= 0.001
Split Flow NTrial= 30
Split Flow Tol= 0.02
Split Flow Ratio= 0.02
Log Output Level= 0
Friction Slope Method= 1
Unsteady Friction Slope Method= 2
Unsteady Bridges Friction Slope Method= 1
Parabolic Critical Depth
Global Vel Dist=  1 , 1 , 1
Global Log Level= 0
CheckData=True
Encroach Param= -1, 0, 0, 0
BEGIN DESCRIPTION:
Multiple Run
END DESCRIPTION:

--- Stream0436.f01 (steady flow) ---

Flow Title=Multiple
Number of Profiles=7
Profile Names=10-year,25-year,50-year,1pct_min,100-year,1pct_plu,500-year
River Rch & RM= Stream0436,Reach-1,1330
    1836    3250    4644    3205    6395   12760   11987
Boundary for River Rch & Prof#=Stream0436,Reach-1,1
Up Type=0
Dn Type=3
Dn Slope=0.005
Boundary for River Rch & Prof#=Stream0436,Reach-1,2
Up Type=0
Dn Type=3
Dn Slope=0.005
Boundary for River Rch & Prof#=Stream0436,Reach-1,3
Up Type=0
Dn Type=3
Dn Slope=0.005
Boundary for River Rch & Prof#=Stream0436,Reach-1,4
Up Type=0
Dn Type=3
Dn Slope=0.005
Boundary for River Rch & Prof#=Stream0436,Reach-1,5
Up Type=0
Dn Type=3
Dn Slope=0.005
Boundary for River Rch & Prof#=Stream0436,Reach-1,6
Up Type=0
Dn Type=3
Dn Slope=0.005
Boundary for River Rch & Prof#=Stream0436,Reach-1,7
Up Type=0
Dn Type=3
Dn Slope=0.005

--- Stream0436.g01 (geometry) ---

Geom Title=Existing Conditions

River Reach=Stream0436,Reach-1
Reach XY= 30
      1875375.00     13948725.00      1875406.81     13948725.14
      1875423.51     13948728.69      1875434.59     13948736.14
      1875461.85     13948761.81      1875472.75     13948769.88
      1875485.67     13948774.38      1875500.00     13948775.47
      1875514.32     13948774.26      1875527.18     13948769.63
      1875538.04     13948761.45      1875568.92     13948733.19
      1875580.93     13948727.28      1875595.03     13948725.08
      1876250.08     13948724.80      1876264.50     13948726.22
      1876277.33     13948730.75      1876288.14     13948738.79
      1876315.36     13948764.15      1876326.57     13948771.23
      1876340.22     13948774.49      1876364.83     13948775.50
      1876450.07     13948775.23      1876469.06     13948772.75
      1876477.33     13948769.26      1876484.64     13948764.15
      1876518.94     13948733.14      1876526.57     13948728.78
      1876540.22     13948725.52      1876775.00     13948725.00

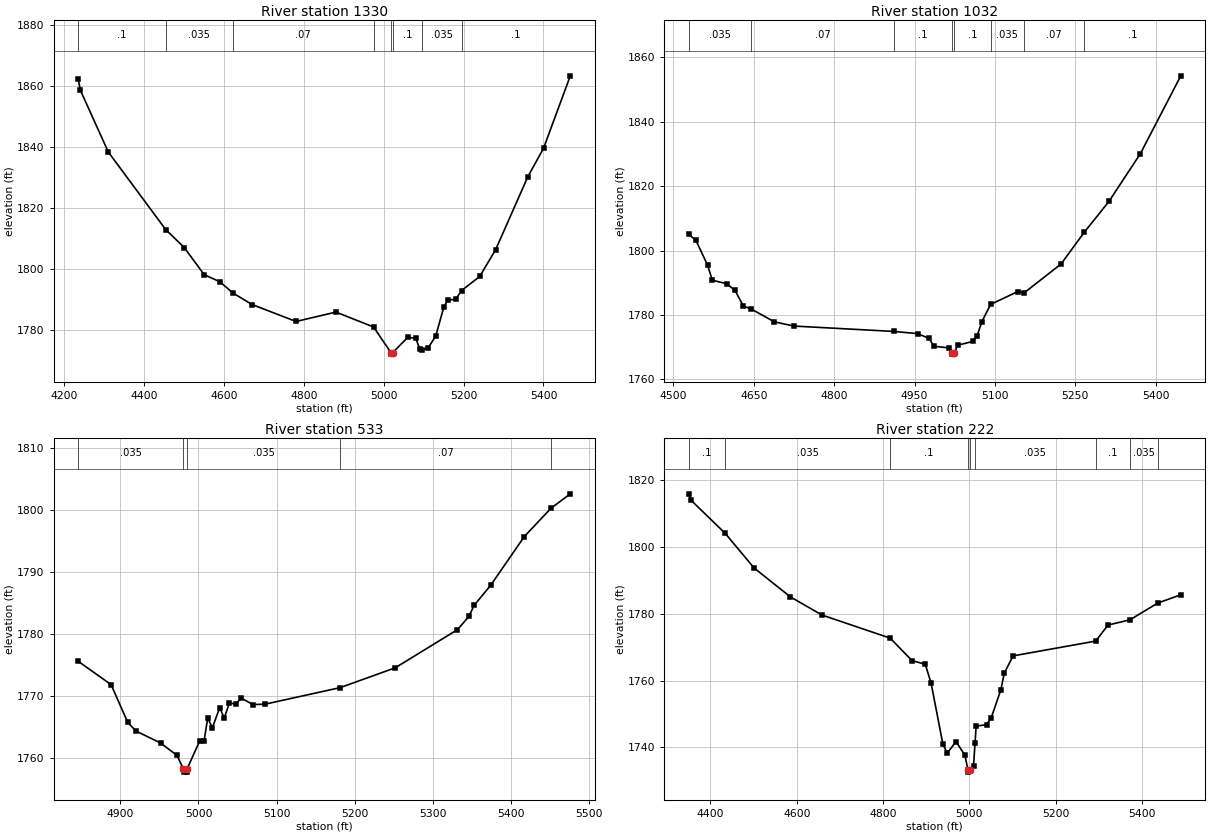
Type RM Length L Ch R = 1,1330,298,298,298
BEGIN DESCRIPTION:
Stream0436 3.0
END DESCRIPTION:
XS GIS Cut Line= 2
      1875498.48     13949540.65      1875490.85     13948307.98
#Sta/Elev= 30
  4234.6 1862.16  4240.3 1858.42  4310.3 1838.20  4453.9 1812.83  4500.3 1806.94
  4550.3 1798.06  4590.3 1795.68  4621.2 1792.14  4670.3 1788.27  4780.3 1782.73
  4880.3 1785.80  4974.5 1780.92  5018.0 1772.53  5018.3 1772.03  5022.5 1772.53
  5060.3 1777.54  5080.3 1777.22  5090.3 1773.69  5096.7 1773.41  5110.3 1773.88
  5130.3 1777.96  5150.3 1787.40  5160.3 1789.69  5180.3 1790.04  5195.0 1792.86
  5240.3 1797.46  5280.3 1806.25  5360.3 1829.98  5400.3 1839.47  5467.3 1863.19
#Mann=8,-1,0
  4234.6     0.1       0  4453.9   0.035       0  4621.2    0.07       0
  4974.5     0.1       0  5018.0    0.05       0  5022.5     0.1       0
  5096.7   0.035       0  5195.0     0.1       0
Bank Sta=5018,5022.5
Exp/Cntr=0.3,0.1

Type RM Length L Ch R = 1,1032,499,499,499
BEGIN DESCRIPTION:
Stream0436 2.0
END DESCRIPTION:
XS GIS Cut Line= 3
      1876024.99     13949124.98      1875775.00     13948725.00
      1875575.00     13948324.99
#Sta/Elev= 30
  4528.3 1805.02  4541.8 1803.19  4563.7 1795.44  4572.5 1790.79  4599.6 1789.68
  4615.0 1787.61  4630.3 1782.79  4645.6 1781.81  4688.1 1777.89  4724.6 1776.57
  4911.2 1774.90  4955.8 1774.22  4977.0 1772.75  4986.4 1770.30  5014.0 1769.79
  5020.1 1768.36  5020.4 1767.86  5024.6 1768.36  5030.7 1770.63  5058.7 1771.79
  5067.1 1773.60  5075.4 1777.81  5092.0 1783.27  5142.5 1787.25  5154.9 1786.89
  5223.6 1795.82  5266.7 1805.61  5313.0 1815.22  5371.7 1830.04  5447.2 1854.19
#Mann=8,-1,0
  4528.3   0.035       0  4645.6    0.07       0  4911.2     0.1       0
  5020.1    0.05       0  5024.6     0.1       0  5092.0   0.035       0
  5154.9    0.07       0  5266.7     0.1       0
Bank Sta=5020.1,5024.6
Exp/Cntr=0.3,0.1

Type RM Length L Ch R = 1,533,311,311,311
BEGIN DESCRIPTION:
Stream0436 1.0
END DESCRIPTION:
XS GIS Cut Line= 3
      1876225.00     13948875.01      1876275.00     13948725.00
      1876025.01     13948325.02
#Sta/Elev= 30
  4846.0 1775.59  4888.2 1771.80  4909.3 1765.74  4919.8 1764.32  4951.4 1762.37
  4972.5 1760.37  4980.7 1758.16  4981.1 1757.66  4985.0 1757.66  4985.3 1758.16
  5001.5 1762.68  5007.1 1762.68  5011.8 1766.41  5017.7 1764.82  5027.1 1768.07
  5033.0 1766.41  5039.5 1768.83  5048.3 1768.66  5054.2 1769.66  5069.6 1768.59
  5084.9 1768.64  5181.2 1771.32  5251.8 1774.53  5331.4 1780.70  5346.1 1782.84
  5352.6 1784.61  5373.8 1787.85  5416.9 1795.75  5451.1 1800.33  5475.8 1802.66
#Mann=5,-1,0
  4846.0   0.035       0  4980.7   0.035       0  4985.3   0.035       0
  5181.2    0.07       0  5451.1     0.1       0
Bank Sta=4980.7,4985.3
Exp/Cntr=0.3,0.1

Type RM Length L Ch R = 1,222,0,0,0
BEGIN DESCRIPTION:
Stream0436 0.0
END DESCRIPTION:
XS GIS Cut Line= 4
      1876355.35     13949320.62      1876579.59     13948864.00
      1876525.54     13948579.35      1876298.95     13948322.70
#Sta/Elev= 30
  4349.5 1815.87  4355.1 1813.93  4433.7 1804.12  4501.2 1793.68  4585.5 1785.01
  4658.5 1779.60  4816.8 1772.67  4867.4 1765.94  4897.9 1764.88  4911.4 1759.26
  4938.6 1741.12  4948.8 1738.24  4969.2 1741.74  4989.5 1737.73  4997.4 1733.08
  4997.7 1732.58  5002.0 1733.08  5009.9 1734.53  5013.3 1741.22  5015.9 1746.33
  5040.4 1746.80  5050.6 1748.76  5073.2 1757.23  5081.1 1762.19  5101.5 1767.37
  5293.1 1771.80  5321.5 1776.59  5372.4 1778.16  5436.9 1783.18  5490.3 1785.66
#Mann=9,-1,0
  4349.5     0.1       0  4433.7   0.035       0  4816.8     0.1       0
  4997.4    0.05       0  5002.0     0.1       0  5013.3   0.035       0
  5293.1     0.1       0  5372.4   0.035       0  5436.9     0.1       0
Bank Sta=4997.4,5002
Exp/Cntr=0.3,0.1

Chan Stop Cuts=-1