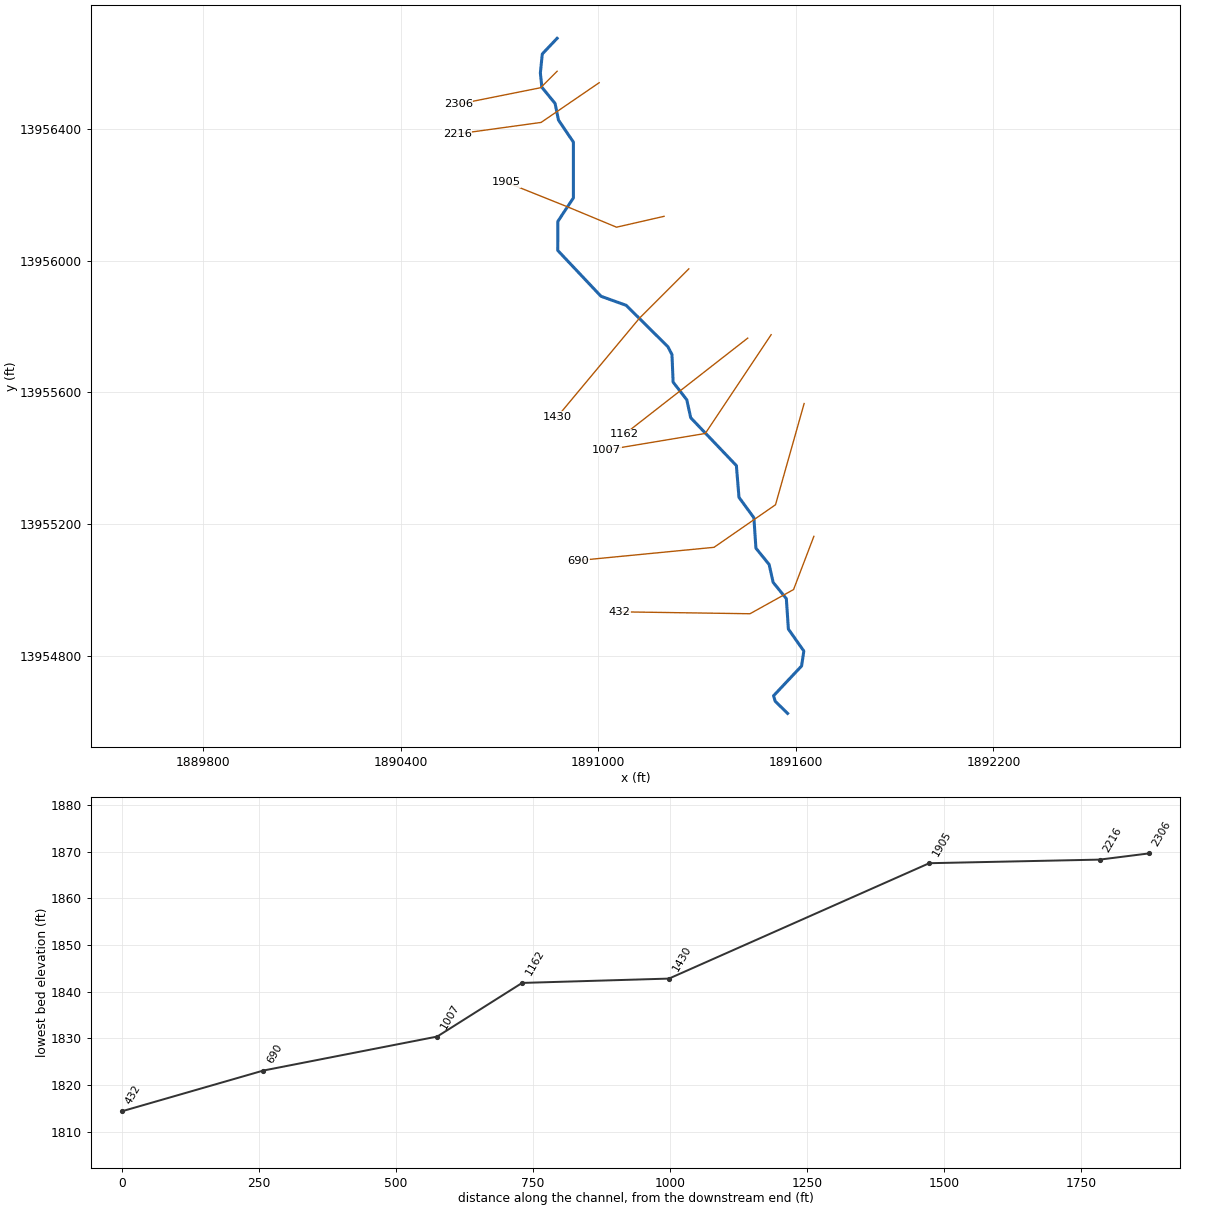
--- Stream0438.prj (project) ---

Proj Title=Stream0438 Base Level Engineering
Current Plan=p01
Default Exp/Contr=0.3,0.1
English Units
Geom File=g01
Flow File=f01
Plan File=p01
BEGIN DESCRIPTION:
Stream0438
END DESCRIPTION:

--- Stream0438.p01 (plan) ---

Plan Title=Multiple Run
Short Identifier=Multiple
Geom File=g01
Flow File=f01
Subcritical Flow
K Sum by GR= 0
Std Step Tol= 0.01
Critical Tol= 0.01
Num of Std Step Trials= 20
Max Error Tol= 0.3
Flow Tol Ratio= 0.001
Split Flow NTrial= 30
Split Flow Tol= 0.02
Split Flow Ratio= 0.02
Log Output Level= 0
Friction Slope Method= 1
Unsteady Friction Slope Method= 2
Unsteady Bridges Friction Slope Method= 1
Parabolic Critical Depth
Global Vel Dist=  1 , 1 , 1
Global Log Level= 0
CheckData=True
Encroach Param= -1, 0, 0, 0
BEGIN DESCRIPTION:
Multiple Run
END DESCRIPTION:

--- Stream0438.f01 (steady flow) ---

Flow Title=Multiple
Number of Profiles=7
Profile Names=10-year,25-year,50-year,1pct_min,100-year,1pct_plu,500-year
River Rch & RM= Stream0438,Reach-1,2306
     567     935    1274     843    1682    3357    2889
Boundary for River Rch & Prof#=Stream0438,Reach-1,1
Up Type=0
Dn Type=3
Dn Slope=0.005
Boundary for River Rch & Prof#=Stream0438,Reach-1,2
Up Type=0
Dn Type=3
Dn Slope=0.005
Boundary for River Rch & Prof#=Stream0438,Reach-1,3
Up Type=0
Dn Type=3
Dn Slope=0.005
Boundary for River Rch & Prof#=Stream0438,Reach-1,4
Up Type=0
Dn Type=3
Dn Slope=0.005
Boundary for River Rch & Prof#=Stream0438,Reach-1,5
Up Type=0
Dn Type=3
Dn Slope=0.005
Boundary for River Rch & Prof#=Stream0438,Reach-1,6
Up Type=0
Dn Type=3
Dn Slope=0.005
Boundary for River Rch & Prof#=Stream0438,Reach-1,7
Up Type=0
Dn Type=3
Dn Slope=0.005

--- Stream0438.g01 (geometry) ---

Geom Title=Existing Conditions

River Reach=Stream0438,Reach-1
Reach XY= 30
      1890875.00     13956675.00      1890830.05     13956627.55
      1890824.18     13956569.93      1890828.67     13956526.57
      1890868.88     13956477.18      1890879.19     13956426.74
      1890924.49     13956359.79      1890924.48     13956190.22
      1890877.16     13956119.02      1890876.96     13956030.89
      1891008.33     13955891.65      1891084.68     13955864.22
      1891211.60     13955738.31      1891223.84     13955714.52
      1891227.33     13955630.97      1891268.86     13955577.17
      1891280.83     13955522.70      1891419.48     13955377.43
      1891427.36     13955280.98      1891472.65     13955219.03
      1891478.83     13955126.58      1891518.89     13955077.18
      1891531.11     13955022.82      1891571.17     13954973.42
      1891577.38     13954880.97      1891624.28     13954814.29
      1891617.49     13954768.94      1891532.27     13954678.33
      1891537.51     13954661.66      1891575.00     13954625.00

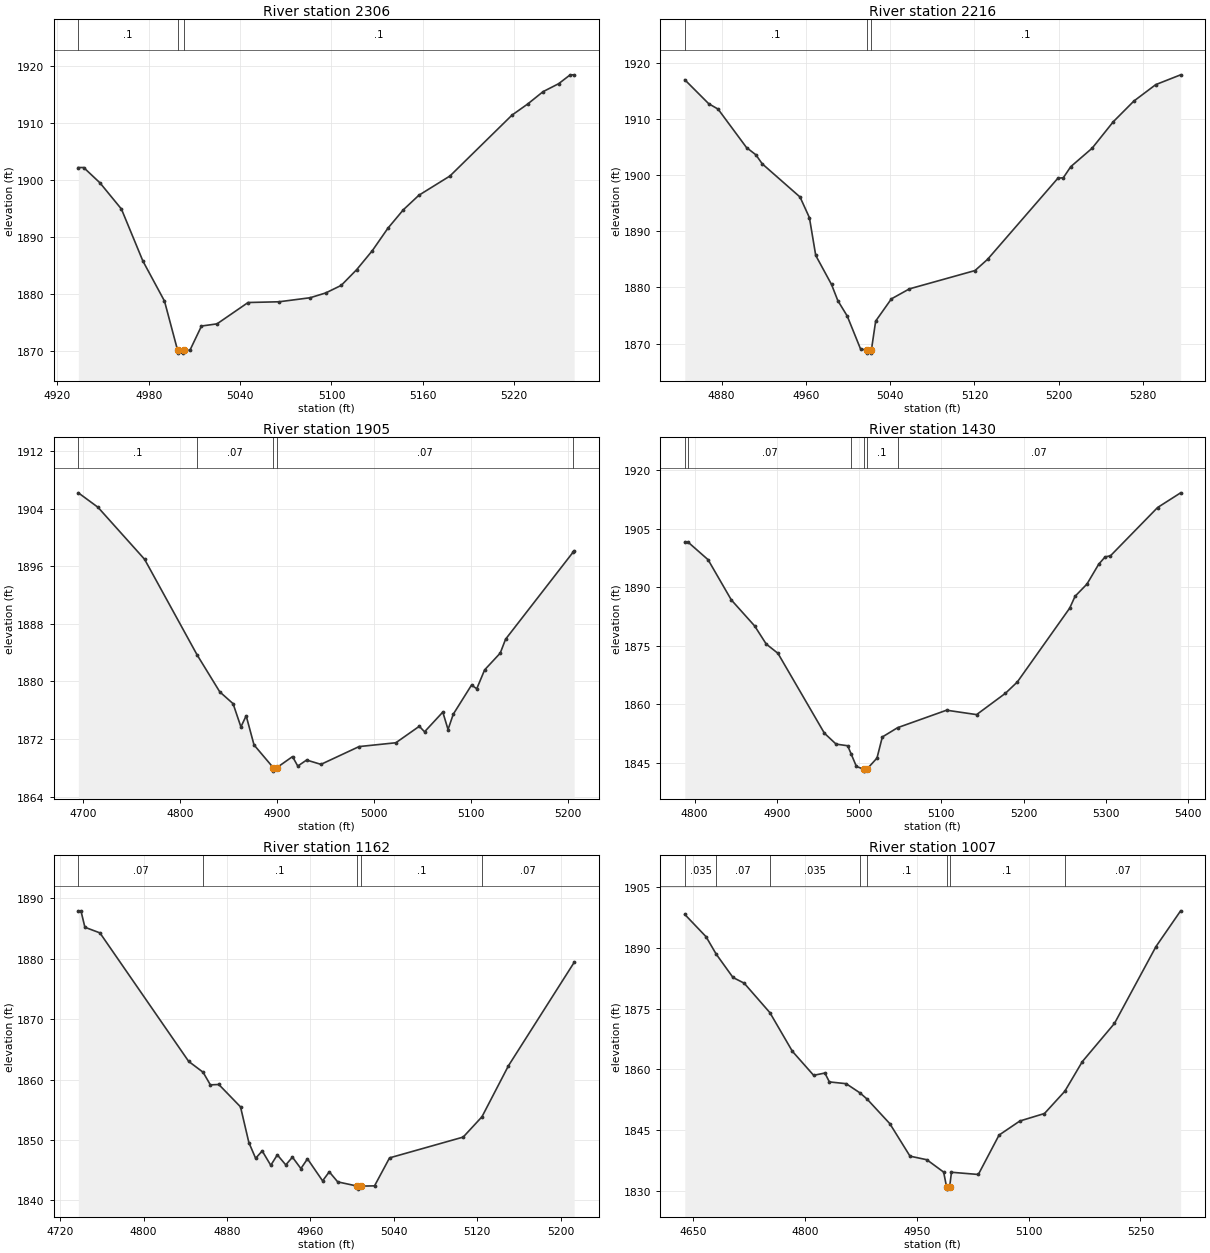
Type RM Length L Ch R = 1,2306,90,90,90
BEGIN DESCRIPTION:
Stream0438 4.0
END DESCRIPTION:
XS GIS Cut Line= 3
      1890875.01     13956575.01      1890825.00     13956525.00
      1890574.97     13956474.99
#Sta/Elev= 30
  4933.7 1902.25  4937.2 1902.25  4947.9 1899.56  4962.0 1894.96  4976.1 1885.83
  4990.3 1878.79  4998.9 1870.15  4999.1 1869.65  5002.6 1869.65  5002.9 1870.15
  5007.0 1870.15  5014.6 1874.41  5024.8 1874.79  5045.2 1878.54  5065.6 1878.67
  5086.0 1879.38  5096.2 1880.22  5106.4 1881.55  5116.6 1884.33  5126.8 1887.64
  5137.0 1891.57  5147.2 1894.83  5157.4 1897.38  5177.8 1900.76  5218.6 1911.46
  5228.8 1913.39  5239.0 1915.58  5249.2 1916.97  5256.8 1918.53  5259.4 1918.53
#Mann=3,-1,0
  4933.7     0.1       0  4998.9    0.05       0  5002.9     0.1       0
Bank Sta=4998.9,5002.9
Exp/Cntr=0.3,0.1

Type RM Length L Ch R = 1,2216,311,311,311
BEGIN DESCRIPTION:
Mapping XS 5e20ec2e
END DESCRIPTION:
XS GIS Cut Line= 3
      1891002.68     13956540.16      1890826.40     13956419.62
      1890571.66     13956384.53
#Sta/Elev= 30
  4845.0 1916.95  4867.7 1912.69  4876.6 1911.73  4903.6 1904.89  4912.5 1903.60
  4918.5 1902.00  4954.4 1896.09  4963.3 1892.42  4969.3 1885.70  4984.3 1880.53
  4990.3 1877.65  4999.2 1874.92  5011.8 1869.08  5018.1 1868.82  5018.4 1868.32
  5021.9 1868.32  5022.1 1868.82  5026.2 1874.02  5041.1 1877.97  5058.2 1879.75
  5120.5 1883.01  5132.4 1885.00  5199.3 1899.46  5204.3 1899.51  5211.4 1901.49
  5231.6 1904.76  5251.8 1909.49  5271.3 1913.16  5292.1 1916.09  5315.7 1917.83
#Mann=3,-1,0
  4845.0     0.1       0  5018.1    0.05       0  5022.1     0.1       0
Bank Sta=5018.1,5022.1
Exp/Cntr=0.3,0.1

Type RM Length L Ch R = 1,1905,475,475,475
BEGIN DESCRIPTION:
Stream0438 3.0
END DESCRIPTION:
XS GIS Cut Line= 4
      1891199.90     13956134.46      1891055.46     13956101.48
      1890906.89     13956163.17      1890719.36     13956238.44
#Sta/Elev= 30
  4695.3 1906.20  4715.5 1904.20  4763.6 1896.97  4817.7 1883.70  4841.1 1878.56
  4854.8 1876.92  4862.9 1873.69  4868.3 1875.24  4876.4 1871.19  4896.1 1868.05
  4896.3 1867.55  4900.1 1868.05  4916.1 1869.57  4921.5 1868.25  4930.6 1869.09
  4945.4 1868.49  4984.7 1870.96  5022.6 1871.49  5046.8 1873.78  5052.2 1873.01
  5071.0 1875.75  5076.4 1873.33  5081.8 1875.46  5100.6 1879.50  5106.0 1878.99
  5114.1 1881.61  5130.2 1883.94  5135.7 1885.87  5205.7 1898.03  5206.4 1898.15
#Mann=5,-1,0
  4695.3     0.1       0  4817.7    0.07       0  4896.1    0.05       0
  4900.1    0.07       0  5205.7     0.1       0
Bank Sta=4896.1,4900.1
Exp/Cntr=0.3,0.1

Type RM Length L Ch R = 1,1430,268,268,268
BEGIN DESCRIPTION:
Stream0438 2.0
END DESCRIPTION:
XS GIS Cut Line= 3
      1891275.01     13955975.01      1891125.00     13955825.00
      1890874.98     13955524.97
#Sta/Elev= 30
  4788.1 1901.63  4792.4 1901.50  4816.4 1897.05  4844.7 1886.72  4873.0 1880.06
  4887.1 1875.41  4901.3 1873.04  4957.8 1852.54  4972.0 1849.74  4986.1 1849.32
  4990.5 1847.12  4996.7 1844.01  5005.4 1843.31  5005.7 1842.81  5009.4 1843.31
  5021.7 1846.15  5028.2 1851.57  5046.8 1853.96  5106.3 1858.44  5142.8 1857.31
  5177.9 1862.79  5192.3 1865.68  5256.0 1884.64  5262.5 1887.67  5276.9 1890.79
  5291.2 1895.89  5299.0 1897.77  5305.5 1898.05  5362.8 1910.44  5390.8 1914.21
#Mann=6,-1,0
  4788.1     0.1       0  4792.4    0.07       0  4990.5     0.1       0
  5005.4    0.05       0  5009.4     0.1       0  5046.8    0.07       0
Bank Sta=5005.4,5009.4
Exp/Cntr=0.3,0.1

Type RM Length L Ch R = 1,1162,155,155,155
BEGIN DESCRIPTION:
Mapping XS fa3bdbc7
END DESCRIPTION:
XS GIS Cut Line= 2
      1891453.91     13955764.66      1891079.13     13955472.18
#Sta/Elev= 30
  4737.4 1887.92  4739.9 1887.92  4743.7 1885.20  4758.1 1884.27  4843.2 1863.01
  4857.0 1861.22  4864.0 1859.13  4872.1 1859.19  4892.9 1855.49  4900.9 1849.59
  4907.4 1846.98  4913.7 1848.20  4921.9 1845.82  4928.2 1847.55  4936.3 1845.89
  4942.7 1847.17  4950.8 1845.28  4957.1 1846.89  4971.6 1843.25  4978.0 1844.74
  4986.1 1843.08  5004.9 1842.38  5005.1 1841.88  5008.9 1842.38  5021.4 1842.42
  5035.8 1847.05  5106.4 1850.49  5124.4 1853.85  5149.8 1862.29  5212.8 1879.39
#Mann=5,-1,0
  4737.4    0.07       0  4857.0     0.1       0  5004.9    0.05       0
  5008.9     0.1       0  5124.4    0.07       0
Bank Sta=5004.9,5008.9
Exp/Cntr=0.3,0.1

Type RM Length L Ch R = 1,1007,317,317,317
BEGIN DESCRIPTION:
Stream0438 1.0
END DESCRIPTION:
XS GIS Cut Line= 3
      1891524.98     13955774.97      1891325.00     13955475.00
      1891024.96     13955424.99
#Sta/Elev= 30
  4639.2 1898.27  4667.7 1892.76  4681.3 1888.46  4703.8 1882.69  4718.8 1881.28
  4753.3 1873.99  4783.4 1864.45  4811.9 1858.51  4827.0 1859.07  4833.0 1856.88
  4855.5 1856.44  4874.0 1854.17  4883.6 1852.63  4914.1 1846.55  4941.1 1838.53
  4963.7 1837.64  4986.2 1834.59  4990.2 1830.88  4990.5 1830.38  4994.2 1830.88
  4996.7 1834.55  5032.7 1834.00  5060.5 1843.74  5088.4 1847.22  5121.4 1849.07
  5148.6 1854.56  5172.1 1861.89  5215.2 1871.33  5270.9 1890.34  5303.9 1899.16
#Mann=8,-1,0
  4639.2   0.035       0  4681.3    0.07       0  4753.3   0.035       0
  4874.0    0.07       0  4883.6     0.1       0  4990.2    0.05       0
  4994.2     0.1       0  5148.6    0.07       0
Bank Sta=4990.2,4994.2
Exp/Cntr=0.3,0.1

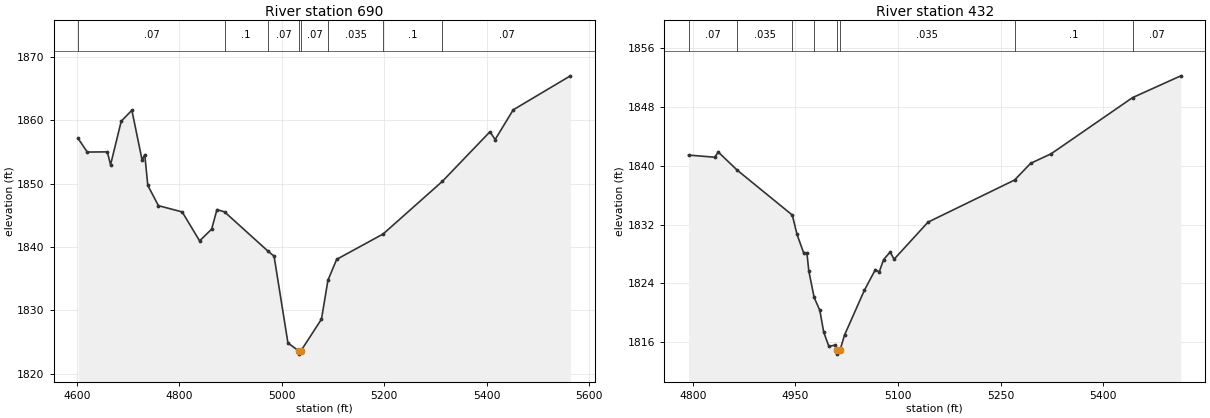
Type RM Length L Ch R = 1,690,258,258,258
BEGIN DESCRIPTION:
Stream0438 0.0
END DESCRIPTION:
XS GIS Cut Line= 4
      1891625.18     13955565.91      1891538.28     13955258.55
      1891351.65     13955129.30      1890938.72     13955089.21
#Sta/Elev= 30
  4602.1 1857.13  4619.9 1854.99  4659.1 1855.02  4665.4 1852.98  4686.2 1859.85
  4707.0 1861.59  4727.0 1853.72  4732.2 1854.58  4738.1 1849.73  4758.9 1846.53
  4805.3 1845.54  4839.3 1840.97  4862.8 1842.83  4873.2 1845.91  4888.0 1845.55
  4972.6 1839.37  4984.7 1838.56  5011.8 1824.86  5033.0 1823.60  5033.2 1823.10
  5037.0 1823.60  5077.3 1828.62  5089.9 1834.76  5107.0 1838.06  5197.7 1842.06
  5313.4 1850.37  5406.4 1858.20  5416.4 1856.96  5451.7 1861.65  5563.4 1867.02
#Mann=8,-1,0
  4602.1    0.07       0  4888.0     0.1       0  4972.6    0.07       0
  5033.0    0.05       0  5037.0    0.07       0  5089.9   0.035       0
  5197.7     0.1       0  5313.4    0.07       0
Bank Sta=5033,5037
Exp/Cntr=0.3,0.1

Type RM Length L Ch R = 1,432,0,0,0
BEGIN DESCRIPTION:
Stream0438 0.1
END DESCRIPTION:
XS GIS Cut Line= 4
      1891654.76     13955162.66      1891593.13     13955001.06
      1891460.85     13954927.57      1891065.48     13954933.39
#Sta/Elev= 30
  4793.7 1841.47  4831.9 1841.18  4837.2 1841.88  4864.8 1839.42  4945.4 1833.30
  4952.2 1830.69  4961.9 1828.17  4966.7 1828.17  4969.5 1825.70  4977.3 1822.09
  4985.6 1820.33  4991.3 1817.36  4998.8 1815.44  5007.3 1815.58  5011.0 1814.87
  5011.3 1814.37  5015.0 1814.87  5021.7 1816.96  5050.8 1823.07  5066.8 1825.87
  5072.5 1825.56  5078.9 1827.25  5088.5 1828.27  5094.2 1827.29  5143.8 1832.34
  5270.3 1838.07  5293.9 1840.35  5323.9 1841.65  5442.8 1849.29  5513.4 1852.26
#Mann=8,-1,0
  4793.7    0.07       0  4864.8   0.035       0  4945.4     0.1       0
  4977.3   0.035       0  5011.0   0.035       0  5015.0   0.035       0
  5270.3     0.1       0  5442.8    0.07       0
Bank Sta=5011,5015
Exp/Cntr=0.3,0.1

Chan Stop Cuts=-1