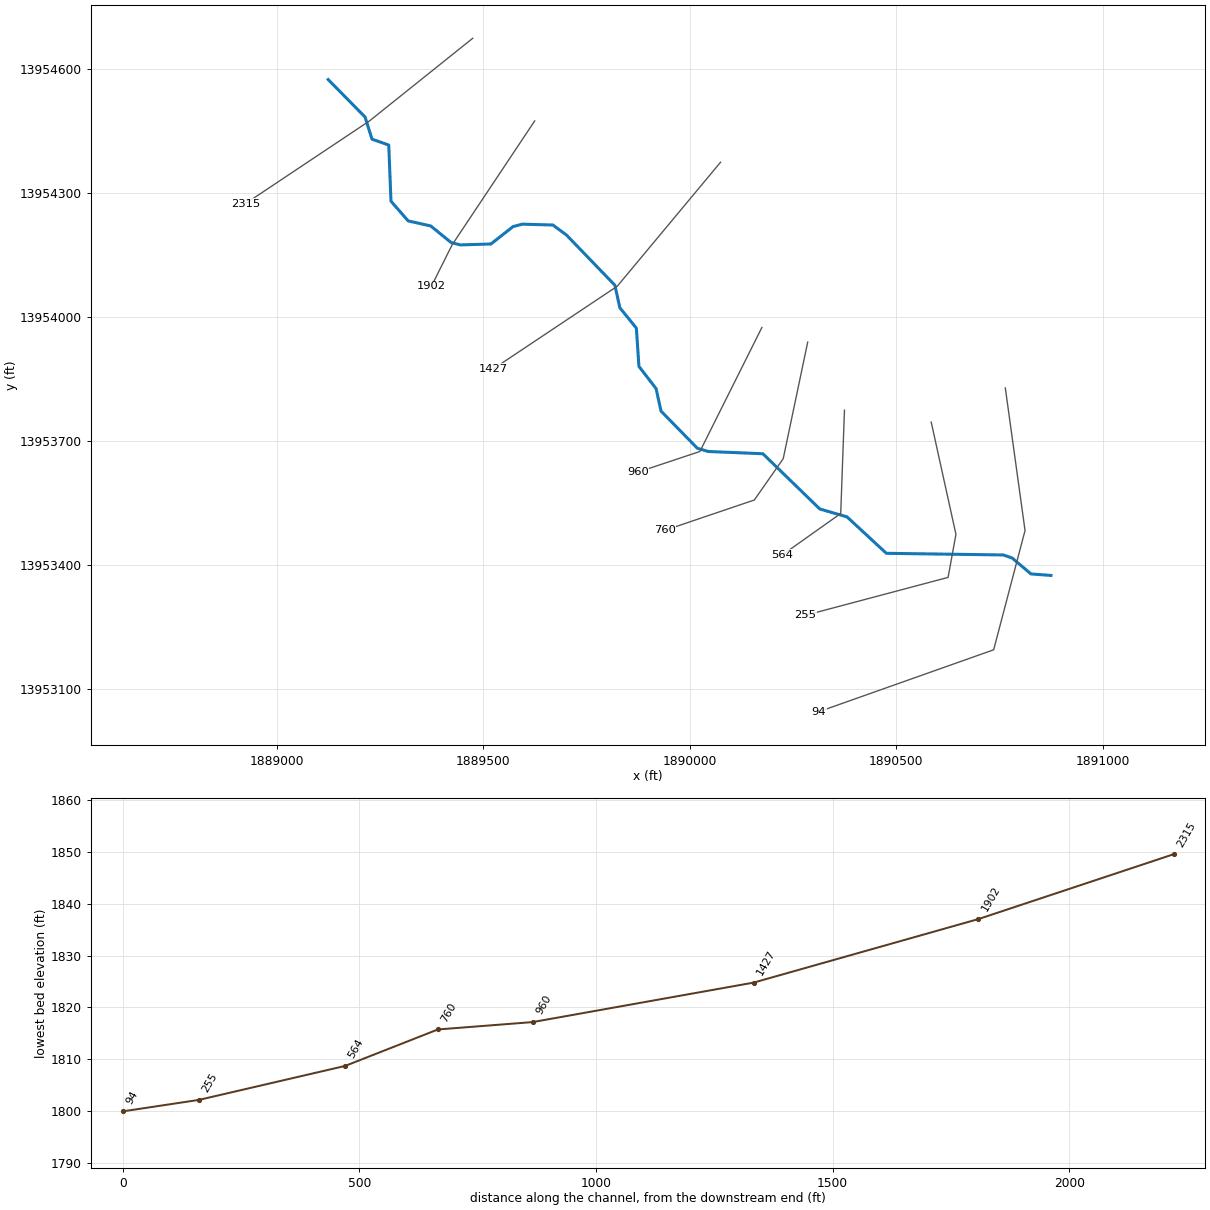
--- Stream0441.prj (project) ---

Proj Title=Stream0441 Base Level Engineering
Current Plan=p01
Default Exp/Contr=0.3,0.1
English Units
Geom File=g01
Flow File=f01
Plan File=p01
BEGIN DESCRIPTION:
Stream0441
END DESCRIPTION:

--- Stream0441.p01 (plan) ---

Plan Title=Multiple Run
Short Identifier=Multiple
Geom File=g01
Flow File=f01
Subcritical Flow
K Sum by GR= 0
Std Step Tol= 0.01
Critical Tol= 0.01
Num of Std Step Trials= 20
Max Error Tol= 0.3
Flow Tol Ratio= 0.001
Split Flow NTrial= 30
Split Flow Tol= 0.02
Split Flow Ratio= 0.02
Log Output Level= 0
Friction Slope Method= 1
Unsteady Friction Slope Method= 2
Unsteady Bridges Friction Slope Method= 1
Parabolic Critical Depth
Global Vel Dist=  1 , 1 , 1
Global Log Level= 0
CheckData=True
Encroach Param= -1, 0, 0, 0
BEGIN DESCRIPTION:
Multiple Run
END DESCRIPTION:

--- Stream0441.f01 (steady flow) ---

Flow Title=Multiple
Number of Profiles=7
Profile Names=10-year,25-year,50-year,1pct_min,100-year,1pct_plu,500-year
River Rch & RM= Stream0441,Reach-1,2315
     650    1078    1476     980    1956    3903    3384
Boundary for River Rch & Prof#=Stream0441,Reach-1,1
Up Type=0
Dn Type=3
Dn Slope=0.005
Boundary for River Rch & Prof#=Stream0441,Reach-1,2
Up Type=0
Dn Type=3
Dn Slope=0.005
Boundary for River Rch & Prof#=Stream0441,Reach-1,3
Up Type=0
Dn Type=3
Dn Slope=0.005
Boundary for River Rch & Prof#=Stream0441,Reach-1,4
Up Type=0
Dn Type=3
Dn Slope=0.005
Boundary for River Rch & Prof#=Stream0441,Reach-1,5
Up Type=0
Dn Type=3
Dn Slope=0.005
Boundary for River Rch & Prof#=Stream0441,Reach-1,6
Up Type=0
Dn Type=3
Dn Slope=0.005
Boundary for River Rch & Prof#=Stream0441,Reach-1,7
Up Type=0
Dn Type=3
Dn Slope=0.005

--- Stream0441.g01 (geometry) ---

Geom Title=Existing Conditions

River Reach=Stream0441,Reach-1
Reach XY= 30
      1889125.00     13954575.00      1889214.21     13954484.44
      1889231.05     13954430.80      1889271.59     13954416.56
      1889276.99     13954280.68      1889318.61     13954233.00
      1889373.22     13954220.76      1889422.67     13954180.64
      1889445.09     13954174.89      1889519.03     13954177.17
      1889572.69     13954219.31      1889595.10     13954225.10
      1889669.11     13954223.04      1889701.87     13954198.85
      1889819.17     13954077.30      1889831.14     13954022.83
      1889871.17     13953973.42      1889877.33     13953880.97
      1889918.86     13953827.17      1889930.82     13953772.69
      1890018.79     13953682.81      1890044.99     13953674.98
      1890177.45     13953669.53      1890315.32     13953535.78
      1890381.04     13953516.82      1890476.47     13953428.55
      1890759.81     13953424.55      1890781.16     13953417.11
      1890826.51     13953378.65      1890875.00     13953375.00

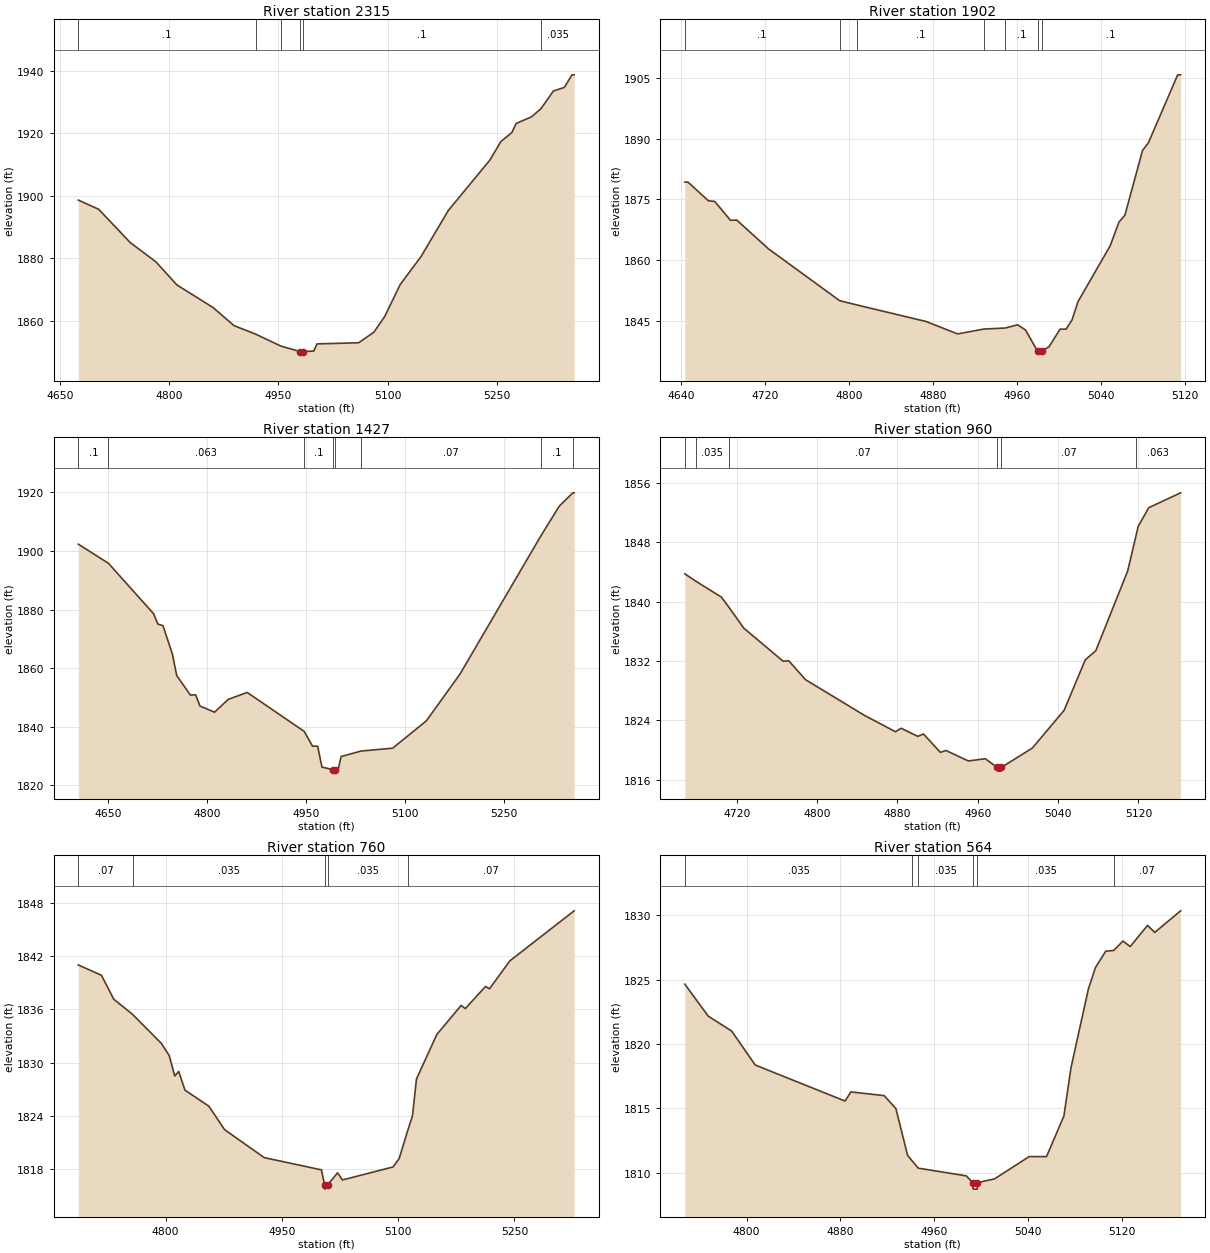
Type RM Length L Ch R = 1,2315,413,413,413
BEGIN DESCRIPTION:
Stream0441 5.0
END DESCRIPTION:
XS GIS Cut Line= 3
      1889475.03     13954675.02      1889225.00     13954475.00
      1888925.04     13954275.02
#Sta/Elev= 30
  4675.2 1898.63  4703.2 1895.67  4746.5 1884.99  4781.7 1878.83  4810.5 1871.42
  4860.1 1864.17  4888.9 1858.37  4918.6 1855.64  4953.4 1851.79  4979.8 1850.04
  4980.0 1849.54  4983.8 1850.04  4998.4 1850.20  5002.9 1852.50  5060.0 1852.86
  5081.0 1856.26  5096.0 1861.36  5117.1 1871.56  5145.6 1880.48  5183.2 1895.32
  5240.3 1911.49  5255.3 1917.42  5270.3 1920.27  5276.3 1923.21  5297.4 1925.34
  5310.4 1927.97  5327.4 1933.63  5342.4 1934.76  5352.9 1938.81  5355.9 1938.81
#Mann=6,-1,0
  4675.2     0.1       0  4918.6    0.07       0  4953.4     0.1       0
  4979.8    0.05       0  4983.8     0.1       0  5310.4   0.035       0
Bank Sta=4979.8,4983.8
Exp/Cntr=0.3,0.1

Type RM Length L Ch R = 1,1902,475,475,475
BEGIN DESCRIPTION:
Stream0441 4.0
END DESCRIPTION:
XS GIS Cut Line= 3
      1889624.98     13954474.97      1889425.00     13954175.00
      1889375.01     13954075.02
#Sta/Elev= 30
  4643.6 1879.26  4646.6 1879.26  4666.1 1874.64  4672.1 1874.49  4687.1 1869.83
  4693.1 1869.88  4723.2 1862.80  4791.1 1849.98  4807.8 1848.91  4873.4 1844.84
  4903.5 1841.77  4928.6 1842.98  4948.8 1843.23  4960.6 1844.03  4968.1 1842.76
  4979.6 1837.53  4979.8 1837.03  4983.6 1837.53  4990.6 1838.62  5001.1 1842.96
  5006.9 1842.96  5012.5 1845.25  5018.1 1849.71  5048.8 1863.53  5057.2 1869.40
  5062.8 1871.05  5079.6 1887.06  5085.2 1888.95  5113.1 1905.74  5115.9 1905.74
#Mann=7,-1,0
  4643.6     0.1       0  4791.1    0.07       0  4807.8     0.1       0
  4928.6    0.07       0  4948.8     0.1       0  4979.6    0.05       0
  4983.6     0.1       0
Bank Sta=4979.6,4983.6
Exp/Cntr=0.3,0.1

Type RM Length L Ch R = 1,1427,467,467,467
BEGIN DESCRIPTION:
Stream0441 3.0
END DESCRIPTION:
XS GIS Cut Line= 3
      1890074.98     13954374.98      1889825.00     13954075.00
      1889525.03     13953875.02
#Sta/Elev= 30
  4605.1 1902.33  4650.7 1895.81  4719.0 1878.60  4725.5 1875.05  4733.3 1874.48
  4747.6 1864.78  4754.1 1857.45  4774.9 1850.77  4782.8 1850.86  4789.3 1847.04
  4811.4 1844.92  4832.2 1849.30  4860.9 1851.66  4947.3 1838.35  4959.8 1833.30
  4967.6 1833.31  4974.1 1826.16  4990.3 1825.28  4990.6 1824.78  4994.3 1825.28
  4998.6 1825.28  5003.1 1829.76  5033.3 1831.64  5081.2 1832.62  5132.3 1841.97
  5183.4 1858.02  5305.4 1905.06  5333.6 1915.35  5354.1 1919.88  5356.1 1919.88
#Mann=8,-1,0
  4605.1     0.1       0  4650.7   0.063       0  4947.3     0.1       0
  4990.3    0.05       0  4994.3     0.1       0  5033.3    0.07       0
  5305.4     0.1       0  5354.1    0.07       0
Bank Sta=4990.3,4994.3
Exp/Cntr=0.3,0.1

Type RM Length L Ch R = 1,960,200,200,200
BEGIN DESCRIPTION:
Stream0441 2.0
END DESCRIPTION:
XS GIS Cut Line= 3
      1890175.02     13953975.04      1890025.00     13953675.00
      1889874.97     13953624.99
#Sta/Elev= 30
  4668.4 1843.76  4679.2 1842.78  4704.8 1840.62  4712.4 1839.24  4727.1 1836.44
  4766.3 1831.98  4771.9 1832.04  4788.6 1829.49  4847.3 1824.68  4878.1 1822.48
  4883.7 1822.95  4900.4 1821.85  4906.0 1822.18  4922.8 1819.70  4928.4 1819.95
  4950.7 1818.54  4967.5 1818.84  4979.5 1817.67  4979.7 1817.17  4983.2 1817.17
  4983.5 1817.67  5014.4 1820.28  5046.0 1825.36  5067.1 1832.17  5077.6 1833.40
  5109.3 1844.14  5117.5 1848.84  5119.8 1850.16  5130.3 1852.67  5162.0 1854.67
#Mann=6,-1,0
  4668.4   0.094       0  4679.2   0.035       0  4712.4    0.07       0
  4979.5    0.05       0  4983.5    0.07       0  5117.5   0.063       0
Bank Sta=4979.5,4983.5
Exp/Cntr=0.3,0.1

Type RM Length L Ch R = 1,760,196,196,196
BEGIN DESCRIPTION:
Mapping XS e1393327
END DESCRIPTION:
XS GIS Cut Line= 4
      1890286.01     13953939.69      1890226.74     13953657.63
      1890156.79     13953557.58      1889939.62     13953483.98
#Sta/Elev= 30
  4687.5 1841.01  4717.3 1839.85  4733.2 1837.15  4757.4 1835.45  4794.5 1832.18
  4804.7 1830.81  4811.9 1828.50  4817.0 1829.01  4825.1 1826.90  4855.8 1825.10
  4876.2 1822.45  4927.3 1819.30  5001.1 1817.92  5005.2 1816.25  5005.4 1815.75
  5009.2 1816.25  5022.0 1817.59  5028.1 1816.78  5093.5 1818.25  5101.4 1819.20
  5112.2 1822.29  5118.5 1824.00  5123.7 1828.16  5149.9 1833.17  5181.3 1836.45
  5186.6 1836.09  5212.7 1838.58  5218.0 1838.33  5244.1 1841.47  5327.1 1847.11
#Mann=5,-1,0
  4687.5    0.07       0  4757.4   0.035       0  5005.2   0.035       0
  5009.2   0.035       0  5112.2    0.07       0
Bank Sta=5005.2,5009.2
Exp/Cntr=0.3,0.1

Type RM Length L Ch R = 1,564,309,309,309
BEGIN DESCRIPTION:
Stream0441 1.0
END DESCRIPTION:
XS GIS Cut Line= 3
      1890375.00     13953775.01      1890365.95     13953524.90
      1890225.03     13953425.02
#Sta/Elev= 30
  4747.3 1824.66  4767.3 1822.17  4787.3 1821.01  4807.4 1818.37  4884.0 1815.57
  4889.0 1816.28  4917.4 1815.99  4927.4 1814.98  4937.4 1811.34  4941.5 1810.89
  4946.5 1810.35  4987.5 1809.75  4993.0 1809.22  4993.3 1808.72  4996.8 1808.72
  4997.0 1809.22  5011.6 1809.52  5041.1 1811.25  5055.9 1811.25  5070.7 1814.40
  5076.8 1818.17  5091.6 1824.28  5097.7 1825.96  5106.4 1827.22  5113.2 1827.28
  5121.1 1828.01  5127.3 1827.58  5142.1 1829.23  5148.2 1828.68  5170.3 1830.36
#Mann=6,-1,0
  4747.3   0.035       0  4941.5     0.1       0  4946.5   0.035       0
  4993.0   0.035       0  4997.0   0.035       0  5113.2    0.07       0
Bank Sta=4993,4997
Exp/Cntr=0.3,0.1

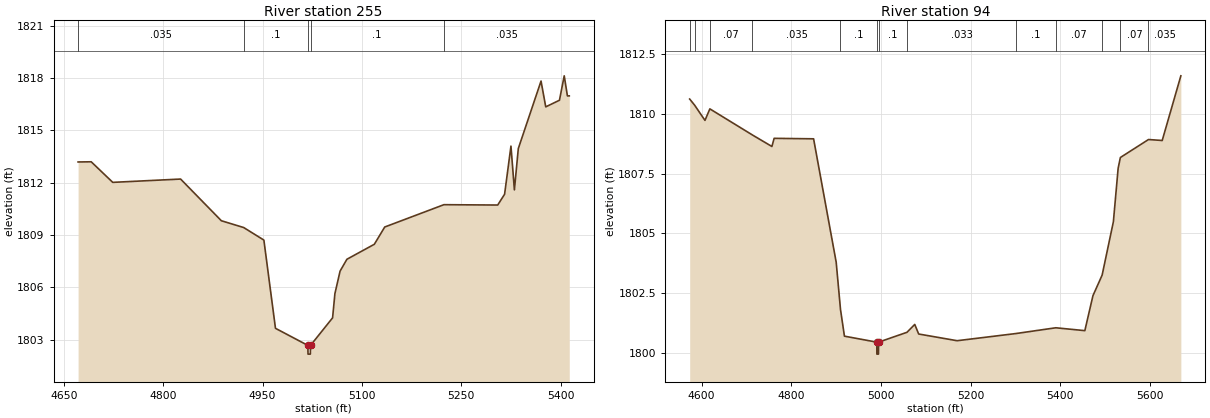
Type RM Length L Ch R = 1,255,161,161,161
BEGIN DESCRIPTION:
Stream0441 0.0
END DESCRIPTION:
XS GIS Cut Line= 4
      1890585.03     13953746.09      1890644.91     13953474.40
      1890625.92     13953370.26      1890280.65     13953278.58
#Sta/Elev= 30
  4671.6 1813.19  4691.4 1813.20  4723.9 1812.02  4826.3 1812.21  4887.8 1809.82
  4921.5 1809.43  4952.0 1808.71  4969.5 1803.65  5018.4 1802.67  5018.6 1802.17
  5022.1 1802.17  5022.4 1802.67  5055.7 1804.25  5059.2 1805.64  5067.0 1806.93
  5077.3 1807.61  5118.7 1808.47  5134.4 1809.46  5223.7 1810.74  5304.9 1810.72
  5315.3 1811.34  5324.9 1814.10  5330.1 1811.59  5336.0 1813.96  5370.3 1817.83
  5377.4 1816.35  5398.1 1816.73  5405.3 1818.13  5410.1 1816.98  5412.9 1816.98
#Mann=5,-1,0
  4671.6   0.035       0  4921.5     0.1       0  5018.4    0.05       0
  5022.4     0.1       0  5223.7   0.035       0
Bank Sta=5018.4,5022.4
Exp/Cntr=0.3,0.1

Type RM Length L Ch R = 1,94,0,0,0
BEGIN DESCRIPTION:
Stream0441 0.1
END DESCRIPTION:
XS GIS Cut Line= 4
      1890764.46     13953828.76      1890812.21     13953483.68
      1890736.25     13953195.05      1890313.09     13953045.31
#Sta/Elev= 30
  4573.3 1810.61  4584.1 1810.36  4607.4 1809.72  4618.3 1810.20  4713.3 1809.11
  4756.7 1808.63  4761.7 1808.97  4849.7 1808.95  4900.1 1803.80  4909.7 1801.83
  4918.5 1800.71  4990.7 1800.46  4990.9 1799.96  4994.4 1799.96  4994.7 1800.46
  5057.9 1800.87  5075.4 1801.20  5084.1 1800.80  5169.9 1800.52  5301.3 1800.82
  5390.0 1801.06  5454.8 1800.94  5472.9 1802.40  5493.4 1803.26  5518.5 1805.49
  5529.1 1807.72  5534.1 1808.17  5596.8 1808.92  5627.4 1808.88  5669.0 1811.58
#Mann=13,-1,0
  4573.3    0.07       0  4584.1   0.035       0  4618.3    0.07       0
  4713.3   0.035       0  4909.7     0.1       0  4990.7    0.05       0
  4994.7     0.1       0  5057.9   0.033       0  5301.3     0.1       0
  5390.0    0.07       0  5493.4   0.035       0  5534.1    0.07       0
  5596.8   0.035       0
Bank Sta=4990.7,4994.7
Exp/Cntr=0.3,0.1

Chan Stop Cuts=-1