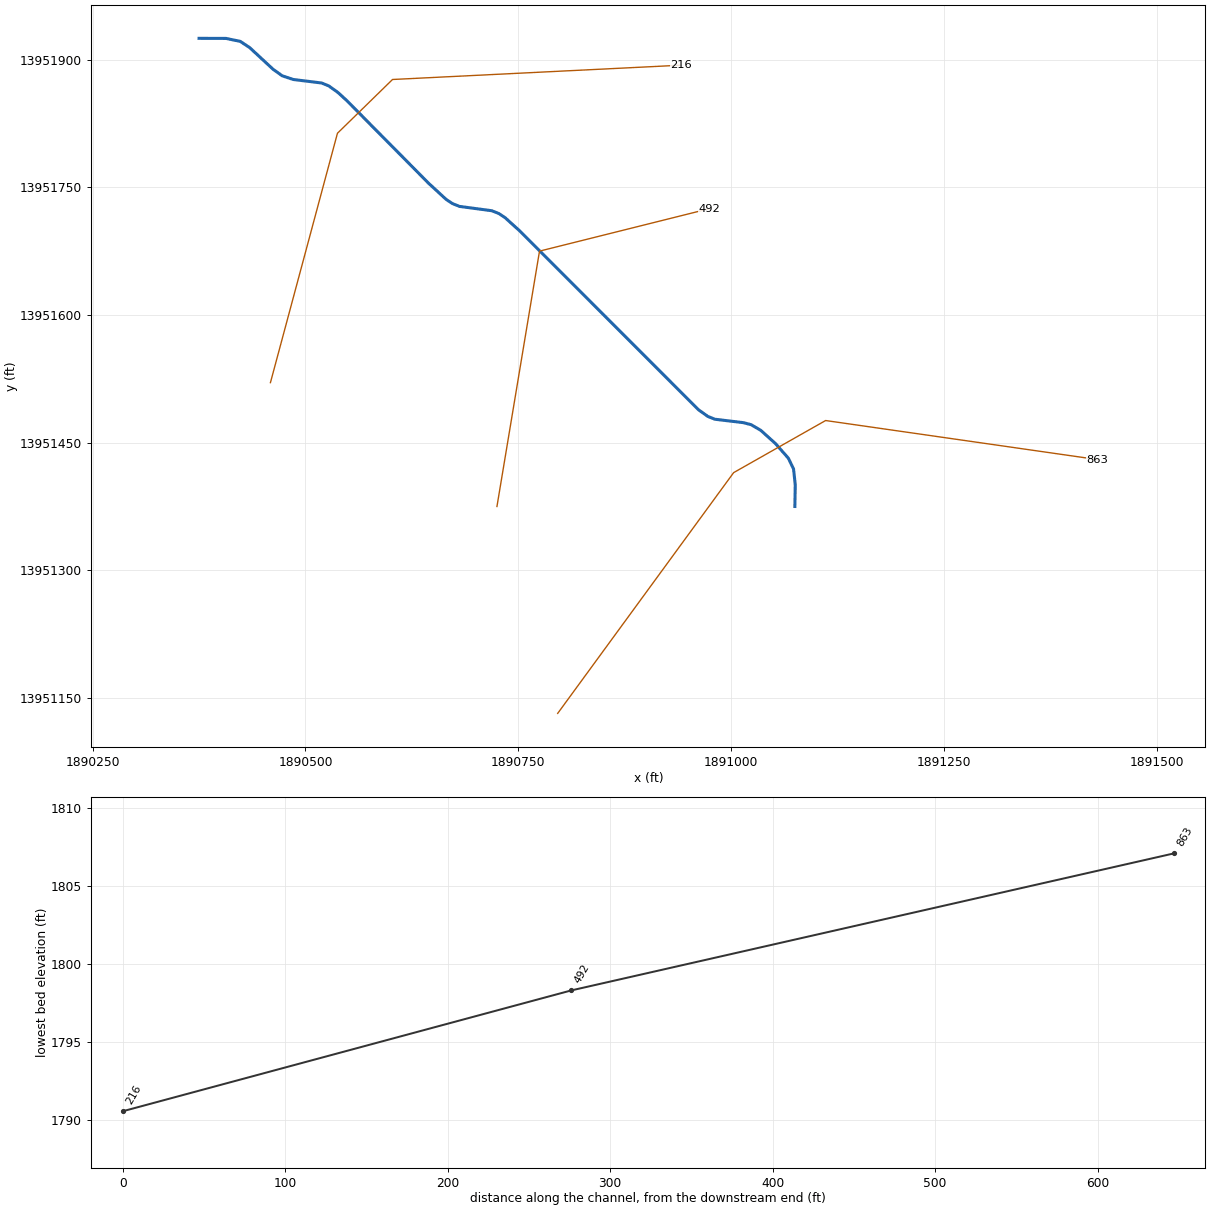
--- Stream0442.prj (project) ---

Proj Title=Stream0442 Base Level Engineering
Current Plan=p01
Default Exp/Contr=0.3,0.1
English Units
Geom File=g01
Flow File=f01
Plan File=p01
Y Axis Title=Elevation
X Axis Title(PF)=Main Channel Distance
X Axis Title(XS)=Station
BEGIN DESCRIPTION:
Stream0442
END DESCRIPTION:
DSS Export Rating Curves= 0
DSS Export Rating Curve Sorted= 0
DSS Export Volume Flow Curves= 0
DXF OffsetX= 0
DXF OffsetY= 0
DXF ScaleX= 1
DXF ScaleY= 10

--- Stream0442.p01 (plan) ---

Plan Title=Multiple Run
Short Identifier=Multiple
Geom File=g01
Flow File=f01
Subcritical Flow
K Sum by GR= 0
Std Step Tol= 0.01
Critical Tol= 0.01
Num of Std Step Trials= 20
Max Error Tol= 0.3
Flow Tol Ratio= 0.001
Split Flow NTrial= 30
Split Flow Tol= 0.02
Split Flow Ratio= 0.02
Log Output Level= 0
Friction Slope Method= 1
Unsteady Friction Slope Method= 2
Unsteady Bridges Friction Slope Method= 1
Parabolic Critical Depth
Global Vel Dist=  1 , 1 , 1
Global Log Level= 0
CheckData=True
Encroach Param= -1, 0, 0, 0
BEGIN DESCRIPTION:
Multiple Run
END DESCRIPTION:

--- Stream0442.f01 (steady flow) ---

Flow Title=Multiple
Program Version=4.10
Number of Profiles= 7
Profile Names=10-year,25-year,50-year,1pct_min,100-year,1pct_plu,500-year
River Rch & RM=Stream0442,Reach-1         ,863
     711    1192    1645    1102    2198    4386    3867
Boundary for River Rch & Prof#=Stream0442,Reach-1         , 1
Up Type= 0
Dn Type= 3
Dn Slope=0.01
Boundary for River Rch & Prof#=Stream0442,Reach-1         , 2
Up Type= 0
Dn Type= 3
Dn Slope=0.01
Boundary for River Rch & Prof#=Stream0442,Reach-1         , 3
Up Type= 0
Dn Type= 3
Dn Slope=0.01
Boundary for River Rch & Prof#=Stream0442,Reach-1         , 4
Up Type= 0
Dn Type= 3
Dn Slope=0.01
Boundary for River Rch & Prof#=Stream0442,Reach-1         , 5
Up Type= 0
Dn Type= 3
Dn Slope=0.01
Boundary for River Rch & Prof#=Stream0442,Reach-1         , 6
Up Type= 0
Dn Type= 3
Dn Slope=0.01
Boundary for River Rch & Prof#=Stream0442,Reach-1         , 7
Up Type= 0
Dn Type= 3
Dn Slope=0.01
DSS Import GetInterval= 0
DSS Import GetPeak= 0
DSS Import FillOption= 0

--- Stream0442.g01 (geometry) ---

Geom Title=Existing Conditions
Program Version=4.10

River Reach=Stream0442      ,Reach-1
Reach XY= 30
        1891075.       13951375.      1891075.46     13951400.49
      1891073.44     13951419.13      1891067.41     13951431.63
      1891052.18     13951448.98      1891034.97     13951464.44
      1891023.54     13951471.14      1891014.47      13951473.5
      1890981.06     13951477.51      1890972.72     13951480.84
       1890961.8     13951488.63      1890751.82      13951698.7
      1890734.68     13951714.22      1890727.29     13951719.14
      1890718.95     13951722.47      1890681.05     13951727.54
      1890672.71     13951730.86      1890665.32     13951735.78
      1890644.84     13951754.62      1890548.47     13951851.99
      1890538.22     13951861.39      1890527.31     13951869.18
      1890518.98     13951872.53      1890485.69     13951876.66
      1890472.76     13951880.97      1890461.85     13951888.78
       1890434.6     13951914.02      1890423.51      13951921.4
      1890406.81      13951924.9        1890375.       13951925.

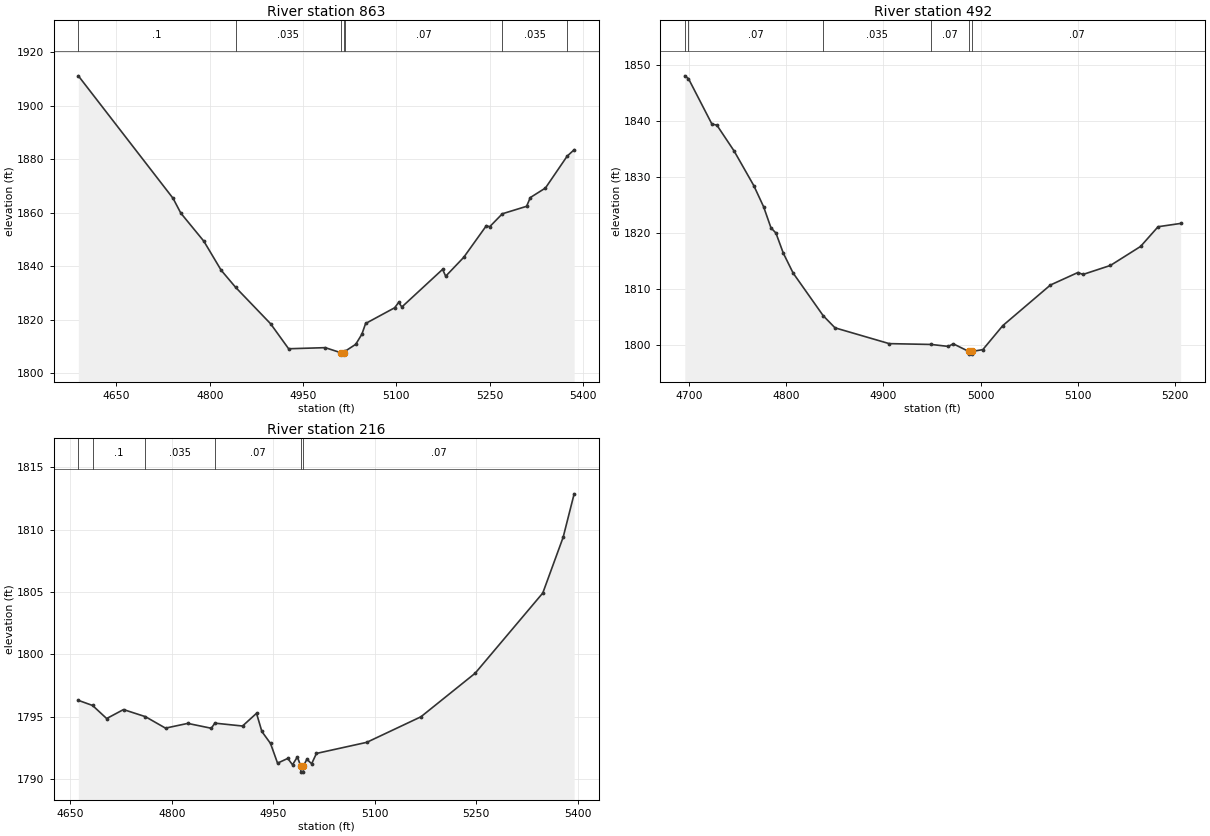
Type RM Length L Ch R = 1 ,863     ,371,371,371
BEGIN DESCRIPTION:
Stream0442 2.0
END DESCRIPTION:
XS GIS Cut Line= 4
      1890796.38     13951131.95      1891003.05     13951414.76
      1891111.12     13951475.99      1891430.75     13951430.11
#Sta/Elev= 30
  4588.7 1911.17  4741.1 1865.33  4753.5 1859.82  4790.6  1849.3  4818.4 1838.45
  4841.6 1832.07  4897.9 1818.43  4926.9 1809.08  4985.8 1809.49  5011.2 1807.57
  5011.4 1807.07  5015.2 1807.57  5017.2 1808.07  5034.8 1810.74  5044.7 1814.52
  5050.7 1818.53  5097.4 1824.41  5103.9 1826.43    5109  1824.7  5174.5 1838.78
  5179.5 1836.21  5208.5 1843.28    5245 1855.14  5250.1 1854.69  5270.6 1859.57
  5309.6 1862.36  5315.6 1865.64  5339.9  1869.2  5374.9 1881.14  5386.1 1883.52
#Mann= 7 ,-1 , 0
  4588.7      .1       0  4841.6    .035       0  5011.2    .035       0
  5015.2    .035       0  5017.2     .07       0  5270.6    .035       0
  5374.9      .1       0
Bank Sta=5011.2,5015.2
XS Rating Curve= 0 ,0
Exp/Cntr=0.3,0.1

Type RM Length L Ch R = 1 ,492     ,276,276,276
BEGIN DESCRIPTION:
Stream0442 1.0
END DESCRIPTION:
XS GIS Cut Line= 3
        1890725.     13951374.99        1890775.       13951675.
        1890975.       13951725.
#Sta/Elev= 30
  4695.6 1848.14  4699.4 1847.63  4723.5  1839.5  4728.6 1839.31  4746.3 1834.69
  4766.6 1828.48  4776.7 1824.69  4784.3 1820.91  4789.4 1819.98    4797 1816.37
  4807.1 1812.81  4838.1 1805.16  4850.2    1803    4906 1800.17  4949.4 1800.02
  4966.8 1799.67  4971.9 1800.14  4987.6 1798.79  4987.9 1798.29  4991.4 1798.29
  4991.6 1798.79  5002.3 1799.09  5022.9  1803.4  5071.9 1810.67  5100.2 1812.91
  5105.4 1812.56  5133.7 1814.18  5164.7 1817.58  5182.7 1821.11  5205.9  1821.7
#Mann= 6 ,-1 , 0
  4695.6      .1       0  4699.4     .07       0  4838.1    .035       0
  4949.4     .07       0  4987.6     .05       0  4991.6     .07       0
Bank Sta=4987.6,4991.6
XS Rating Curve= 0 ,0
Exp/Cntr=0.3,0.1

Type RM Length L Ch R = 1 ,216     ,0,0,0
BEGIN DESCRIPTION:
Stream0442 0.0
END DESCRIPTION:
XS GIS Cut Line= 4
      1890458.88     13951520.49      1890537.61     13951813.46
      1890602.32     13951876.64       1890941.3     13951893.45
#Sta/Elev= 30
  4661.7 1796.31  4682.7  1795.9  4703.6 1794.85  4728.5 1795.57  4760.9    1795
  4790.6 1794.08  4823.5 1794.46  4858.3 1794.07  4863.6 1794.48  4904.5 1794.25
  4925.2 1795.27  4933.1 1793.81  4945.9 1792.85  4956.3 1791.27  4971.4 1791.65
  4978.4 1791.14  4985.6 1791.77  4990.5 1791.05  4990.8 1790.55  4994.3 1790.55
  4994.5 1791.05  4999.7 1791.58  5006.7 1791.22  5013.8 1792.05  5088.2 1792.94
  5168.3 1794.99  5248.4 1798.48  5348.5 1804.92  5378.6 1809.39  5394.9 1812.88
#Mann= 6 ,-1 , 0
  4661.7     .07       0  4682.7      .1       0  4760.9    .035       0
  4863.6     .07       0  4990.5     .05       0  4994.5     .07       0
Bank Sta=4990.5,4994.5
XS Rating Curve= 0 ,0
Exp/Cntr=0.3,0.1

Chan Stop Cuts=-1
Use User Specified Reach Order=0
Composite Channel Slope=5