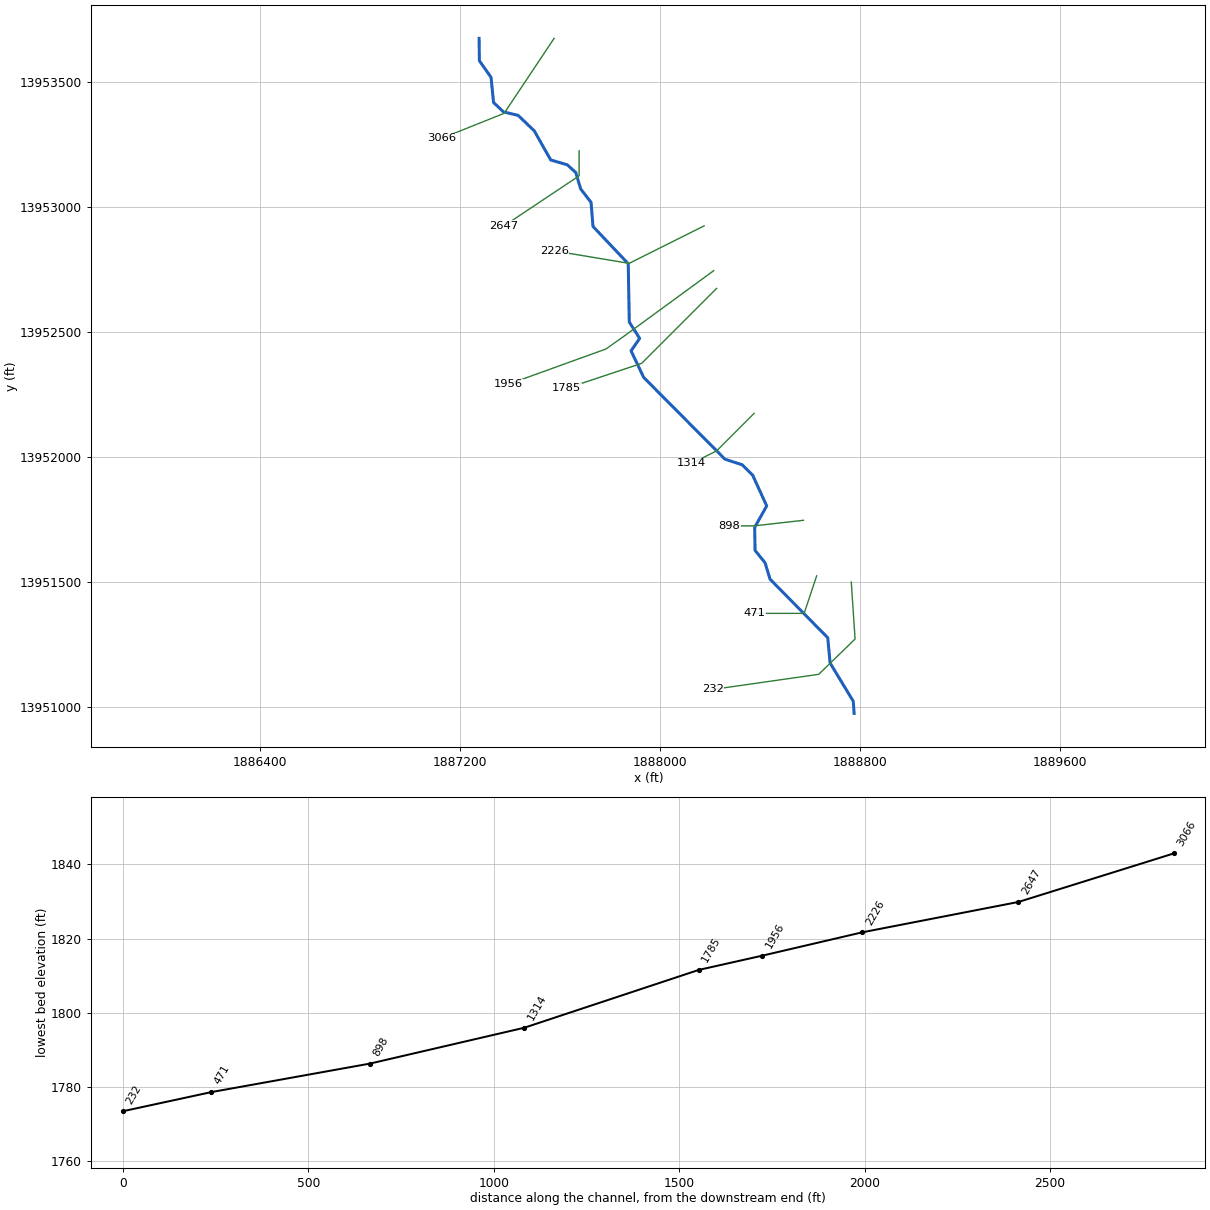
--- Stream0443.prj (project) ---

Proj Title=Stream0443 Base Level Engineering
Current Plan=p01
Default Exp/Contr=0.3,0.1
English Units
Geom File=g01
Flow File=f01
Plan File=p01
Y Axis Title=Elevation
X Axis Title(PF)=Main Channel Distance
X Axis Title(XS)=Station
BEGIN DESCRIPTION:
Stream0443
END DESCRIPTION:
DSS Export Rating Curves= 0
DSS Export Rating Curve Sorted= 0
DSS Export Volume Flow Curves= 0
DXF OffsetX= 0
DXF OffsetY= 0
DXF ScaleX= 1
DXF ScaleY= 10

--- Stream0443.p01 (plan) ---

Plan Title=Multiple Run
Short Identifier=Multiple
Geom File=g01
Flow File=f01
Subcritical Flow
K Sum by GR= 0
Std Step Tol= 0.01
Critical Tol= 0.01
Num of Std Step Trials= 20
Max Error Tol= 0.3
Flow Tol Ratio= 0.001
Split Flow NTrial= 30
Split Flow Tol= 0.02
Split Flow Ratio= 0.02
Log Output Level= 0
Friction Slope Method= 1
Unsteady Friction Slope Method= 2
Unsteady Bridges Friction Slope Method= 1
Parabolic Critical Depth
Global Vel Dist=  1 , 1 , 1
Global Log Level= 0
CheckData=True
Encroach Param= -1, 0, 0, 0
BEGIN DESCRIPTION:
Multiple Run
END DESCRIPTION:

--- Stream0443.f01 (steady flow) ---

Flow Title=Multiple
Program Version=4.10
Number of Profiles= 7
Profile Names=10-year,25-year,50-year,1pct_min,100-year,1pct_plu,500-year
River Rch & RM=Stream0443,Reach-1         ,3066
     558     917    1248     824    1645    3282    2816
Boundary for River Rch & Prof#=Stream0443,Reach-1         , 1
Up Type= 0
Dn Type= 3
Dn Slope=0.01
Boundary for River Rch & Prof#=Stream0443,Reach-1         , 2
Up Type= 0
Dn Type= 3
Dn Slope=0.01
Boundary for River Rch & Prof#=Stream0443,Reach-1         , 3
Up Type= 0
Dn Type= 3
Dn Slope=0.01
Boundary for River Rch & Prof#=Stream0443,Reach-1         , 4
Up Type= 0
Dn Type= 3
Dn Slope=0.01
Boundary for River Rch & Prof#=Stream0443,Reach-1         , 5
Up Type= 0
Dn Type= 3
Dn Slope=0.01
Boundary for River Rch & Prof#=Stream0443,Reach-1         , 6
Up Type= 0
Dn Type= 3
Dn Slope=0.01
Boundary for River Rch & Prof#=Stream0443,Reach-1         , 7
Up Type= 0
Dn Type= 3
Dn Slope=0.01
DSS Import GetInterval= 0
DSS Import GetPeak= 0
DSS Import FillOption= 0

--- Stream0443.g01 (geometry) ---

Geom Title=Existing Conditions
Program Version=4.10

River Reach=Stream0443      ,Reach-1
Reach XY= 30
        1887275.       13953675.      1887276.02     13953585.42
      1887322.66     13953519.03      1887332.74     13953418.55
      1887372.43     13953380.74      1887431.04     13953366.84
      1887495.41     13953305.23      1887561.45     13953188.49
      1887627.51     13953169.24      1887661.52     13953138.56
      1887681.15     13953072.85      1887722.67     13953019.03
      1887730.52     13952922.57      1887871.46     13952773.54
      1887875.65     13952540.16       1887917.2      13952474.9
      1887882.76     13952425.08      1887933.12     13952318.95
      1888258.34     13951991.66      1888327.54     13951969.25
      1888369.27     13951927.55      1888425.29     13951804.83
      1888377.19     13951719.03      1888378.67     13951626.58
      1888418.85     13951577.17      1888438.62     13951511.78
      1888669.48     13951277.43      1888678.83     13951176.59
       1888771.4     13951023.51        1888775.       13950975.

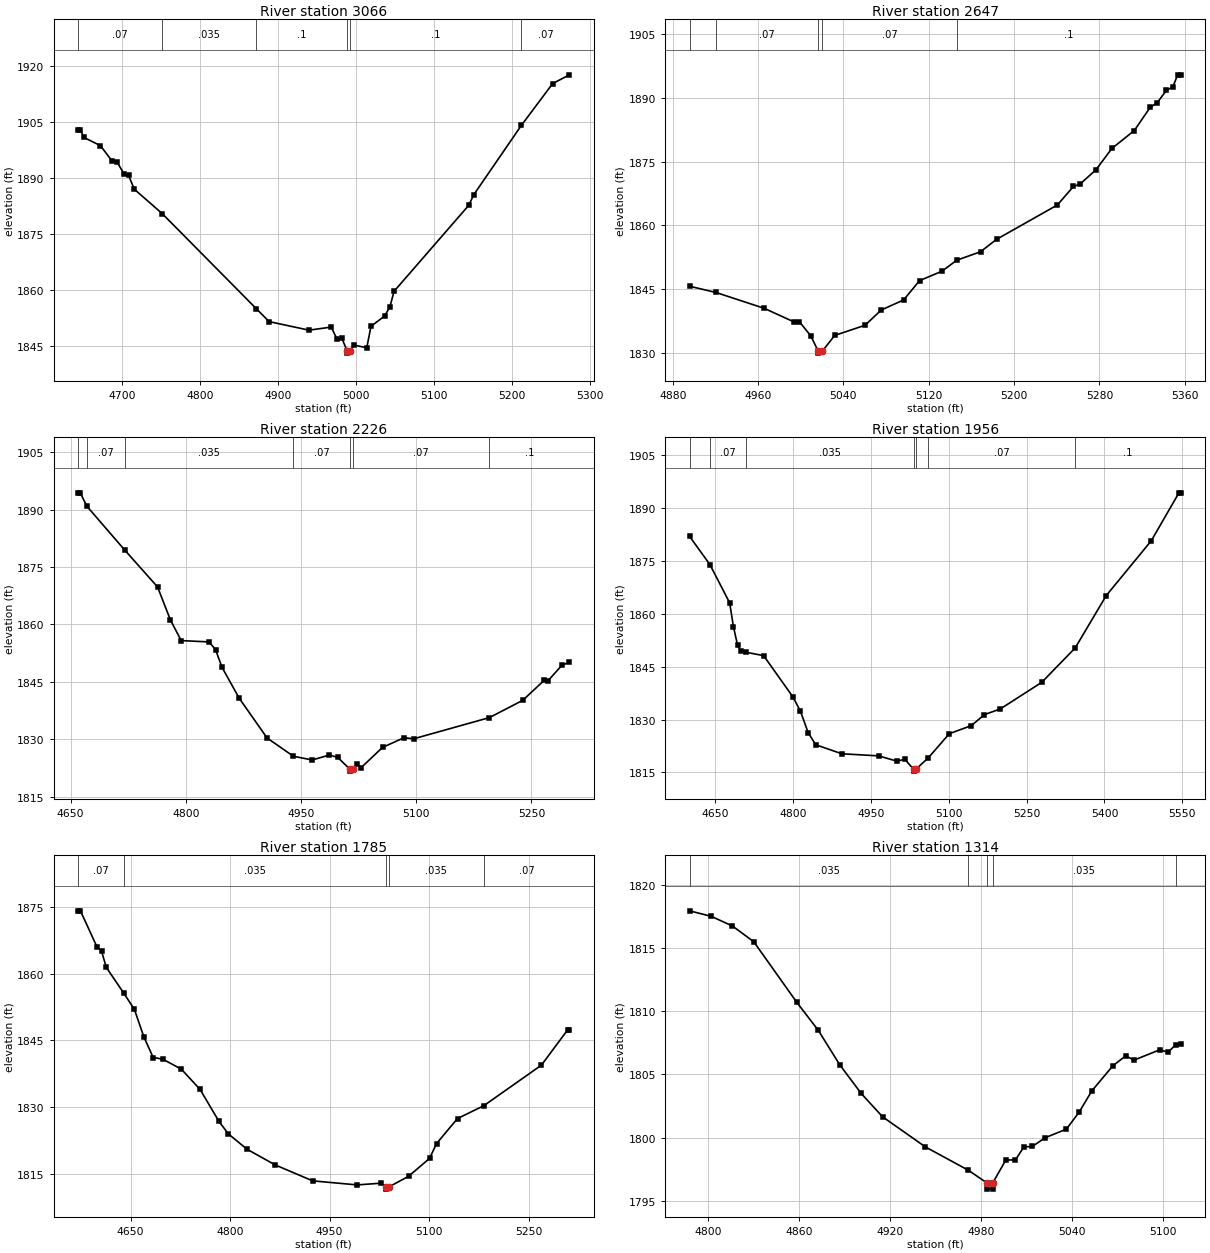
Type RM Length L Ch R = 1 ,3066    ,419,419,419
BEGIN DESCRIPTION:
Stream0443 7.0
END DESCRIPTION:
XS GIS Cut Line= 3
      1887575.02     13953675.02        1887375.       13953375.
      1887125.04     13953275.02
#Sta/Elev= 30
  4643.7 1902.84  4646.7 1902.84  4651.2 1900.84  4672.3 1898.64  4687.3  1894.5
  4693.3 1894.37  4702.3 1891.14  4708.3 1890.66  4715.8 1886.94  4751.5 1880.41
  4872.2 1854.88  4888.6 1851.43  4939.7 1849.14  4968.2 1849.97  4975.7 1846.64
  4981.7 1846.98  4988.8 1843.48    4989 1842.98  4992.8 1843.48  4996.8 1845.17
  5013.7 1844.42  5019.1 1850.17  5036.6 1852.95  5043.3 1855.38  5048.7 1859.57
  5144.3  1882.6    5151 1885.52    5212 1904.12    5252  1915.3  5273.5 1917.64
#Mann= 6 ,-1 , 0
  4643.7     .07       0  4751.5    .035       0  4872.2      .1       0
  4988.8     .05       0  4992.8      .1       0    5212     .07       0
Bank Sta=4988.8,4992.8
XS Rating Curve= 0 ,0
Exp/Cntr=0.3,0.1

Type RM Length L Ch R = 1 ,2647    ,421,421,421
BEGIN DESCRIPTION:
Stream0443 6.0
END DESCRIPTION:
XS GIS Cut Line= 3
        1887675.     13953225.03        1887675.       13953125.
      1887374.99     13952924.99
#Sta/Elev= 30
  4895.7 1845.64  4920.5 1844.17  4965.7 1840.44  4993.2 1837.28  4998.7 1837.28
  5009.3 1833.98  5016.3 1830.38  5016.5 1829.88  5020.3 1830.38  5031.8 1834.05
  5060.3 1836.45  5075.4 1840.03  5096.4 1842.41  5111.4 1846.96  5132.4 1849.19
  5146.3 1851.78  5168.5 1853.76  5183.5 1856.68  5240.6 1864.79  5255.6 1869.15
  5261.6 1869.66  5276.7 1873.08  5291.7 1878.11  5312.7 1882.33  5327.7 1887.84
  5333.8 1888.77  5342.8  1891.8  5348.8 1892.59  5353.3 1895.45  5356.3 1895.45
#Mann= 5 ,-1 , 0
  4895.7      .1       0  4920.5     .07       0  5016.3     .05       0
  5020.3     .07       0  5146.3      .1       0
Bank Sta=5016.3,5020.3
XS Rating Curve= 0 ,0
Exp/Cntr=0.3,0.1

Type RM Length L Ch R = 1 ,2226    ,270,270,270
BEGIN DESCRIPTION:
Stream0443 5.0
END DESCRIPTION:
XS GIS Cut Line= 3
      1888174.99       13952925.        1887875.       13952775.
      1887575.04     13952824.99
#Sta/Elev= 30
  4659.9 1894.38  4662.7 1894.38  4671.2  1890.9  4720.8 1879.38  4763.3  1869.8
  4780.1 1861.15  4794.1 1855.78  4830.4 1855.44  4838.8 1853.41  4847.2  1848.8
  4869.5 1840.76  4905.9 1830.33  4940.2 1825.57  4964.6  1824.6  4986.9 1825.89
  4997.8 1825.29  5013.6 1822.19  5013.8 1821.69  5017.6 1822.19  5023.2  1823.5
  5028.2 1822.59  5056.1 1827.88    5084 1830.41  5096.7 1830.14  5195.2 1835.67
  5238.6 1840.18  5266.5  1845.4  5271.6 1845.31  5289.3 1849.28  5299.4 1850.18
#Mann= 7 ,-1 , 0
  4659.9    .035       0  4671.2     .07       0  4720.8    .035       0
  4940.2     .07       0  5013.6     .05       0  5017.6     .07       0
  5195.2      .1       0
Bank Sta=5013.6,5017.6
XS Rating Curve= 0 ,0
Exp/Cntr=0.3,0.1

Type RM Length L Ch R = 1 ,1956    ,171,171,171
BEGIN DESCRIPTION:
Mapping XS d5d230dc
END DESCRIPTION:
XS GIS Cut Line= 4
      1888213.29     13952745.68      1887862.38     13952489.26
      1887782.46      13952432.5      1887393.03     13952291.84
#Sta/Elev= 30
  4600.5 1882.04  4639.8 1874.02  4677.9 1863.14  4685.1  1856.4  4693.1 1851.15
  4699.3 1849.43  4709.7 1849.11  4743.3 1848.17  4799.7 1836.45  4814.3 1832.37
    4829 1826.33  4843.7 1822.87  4893.9 1820.31  4964.9 1819.71  5000.4  1818.2
  5015.1 1818.77  5032.5 1815.88  5032.7 1815.38  5036.5 1815.88  5060.6 1819.15
  5101.1 1826.01  5143.5  1828.3  5168.8 1831.42  5199.5 1833.04  5279.3  1840.6
  5343.7 1850.37  5403.5 1865.22  5490.2 1880.77  5543.5 1894.38  5547.2 1894.38
#Mann= 7 ,-1 , 0
  4600.5    .035       0  4639.8     .07       0  4709.7    .035       0
  5032.5    .035       0  5036.5    .035       0  5060.6     .07       0
  5343.7      .1       0
Bank Sta=5032.5,5036.5
XS Rating Curve= 0 ,0
Exp/Cntr=0.3,0.1

Type RM Length L Ch R = 1 ,1785    ,471,471,471
BEGIN DESCRIPTION:
Stream0443 4.0
END DESCRIPTION:
XS GIS Cut Line= 3
      1888224.98     13952674.98        1887925.       13952375.
      1887624.97     13952274.99
#Sta/Elev= 30
    4571 1874.17  4574.5 1874.17  4599.3  1866.1  4606.3 1865.12  4613.4 1861.46
  4639.9 1855.63  4655.8    1852    4670 1845.85  4684.1 1841.16  4698.3  1840.8
  4726.5 1838.55  4754.8 1833.98  4783.1 1826.83  4797.3 1823.99  4825.5 1820.52
    4868 1816.99  4924.5  1813.4  4991.7 1812.49  5026.9 1812.87  5035.4 1812.04
  5035.7 1811.54  5039.4 1812.04    5069 1814.42  5100.7 1818.46  5111.2  1821.8
  5142.8 1827.43  5182.4 1830.31  5269.3 1839.45  5308.8 1847.38  5311.5 1847.38
#Mann= 5 ,-1 , 0
    4571     .07       0  4639.9    .035       0  5035.4    .035       0
  5039.4    .035       0  5182.4     .07       0
Bank Sta=5035.4,5039.4
XS Rating Curve= 0 ,0
Exp/Cntr=0.3,0.1

Type RM Length L Ch R = 1 ,1314    ,416,416,416
BEGIN DESCRIPTION:
Stream0443 3.0
END DESCRIPTION:
XS GIS Cut Line= 3
      1888375.01     13952175.01        1888225.       13952025.
      1888124.96     13951974.98
#Sta/Elev= 30
  4787.6 1817.96  4801.8 1817.53  4815.9 1816.76    4830 1815.51  4858.3 1810.72
  4872.5  1808.5  4886.6 1805.78  4900.8  1803.5  4914.9 1801.65  4943.2 1799.26
  4971.4 1797.42  4983.6 1796.42  4983.9 1795.92  4987.4 1795.92  4987.6 1796.42
  4996.2 1798.23  5002.5 1798.23  5008.1 1799.26  5013.7  1799.3  5022.1 1799.99
  5036.1 1800.67  5044.5 1802.01  5052.9  1803.7  5066.8 1805.69  5075.2 1806.47
  5080.8 1806.14  5097.6 1806.95  5103.2 1806.77  5108.2 1807.35  5111.6 1807.42
#Mann= 5 ,-1 , 0
  4787.6    .035       0  4971.4    .035       0  4983.6    .035       0
  4987.6    .035       0  5108.2    .035       0
Bank Sta=4983.6,4987.6
XS Rating Curve= 0 ,0
Exp/Cntr=0.3,0.1

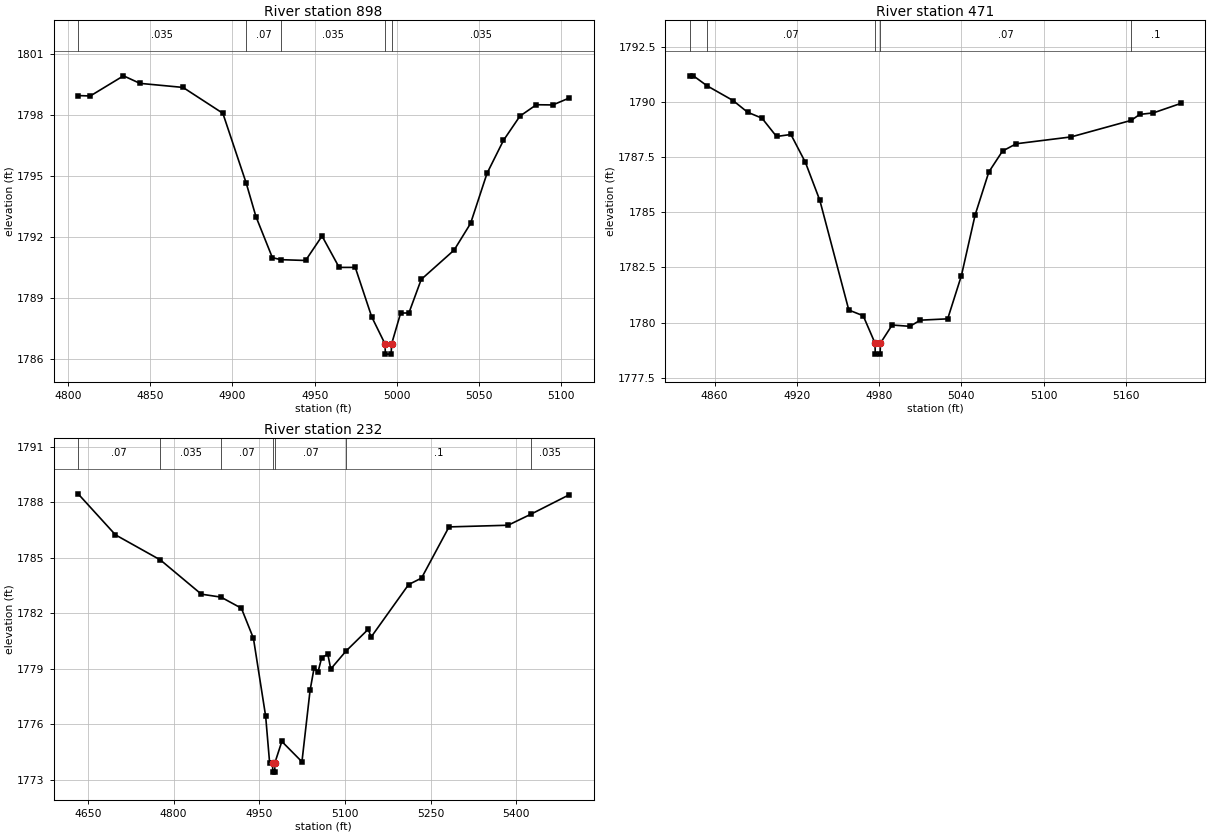
Type RM Length L Ch R = 1 ,898     ,427,427,427
BEGIN DESCRIPTION:
Stream0443 2.0
END DESCRIPTION:
XS GIS Cut Line= 3
      1888572.39     13951747.28        1888375.       13951725.
      1888275.05       13951725.
#Sta/Elev= 30
  4806.2 1798.95  4813.6 1798.93  4833.8 1799.92  4843.8 1799.55    4870 1799.35
  4894.2 1798.08  4908.4 1794.65  4914.3 1793.01  4924.3 1790.99  4929.4 1790.89
  4944.5 1790.85  4954.5 1792.05  4964.9 1790.51  4974.7 1790.51  4984.7 1788.08
  4992.8 1786.75    4993 1786.25  4996.5 1786.25  4996.8 1786.75  5002.3 1788.27
  5007.3 1788.27  5014.8 1789.92  5034.8 1791.36  5044.8 1792.67  5054.8 1795.13
  5064.8 1796.75  5074.8 1797.94  5084.8  1798.5  5094.8 1798.49  5104.8 1798.83
#Mann= 5 ,-1 , 0
  4806.2    .035       0  4908.4     .07       0  4929.4    .035       0
  4992.8    .035       0  4996.8    .035       0
Bank Sta=4992.8,4996.8
XS Rating Curve= 0 ,0
Exp/Cntr=0.3,0.1

Type RM Length L Ch R = 1 ,471     ,239,239,239
BEGIN DESCRIPTION:
Stream0443 1.0
END DESCRIPTION:
XS GIS Cut Line= 3
      1888625.01     13951525.02        1888575.       13951375.
      1888375.04       13951375.
#Sta/Elev= 30
  4841.9 1791.19  4844.6 1791.19  4854.5 1790.74  4873.5 1790.07  4884.1 1789.54
  4894.6 1789.27  4905.2 1788.44  4915.7 1788.53  4926.3 1787.26  4936.8 1785.54
  4957.9 1780.57  4968.4 1780.31    4977 1779.07  4977.2 1778.57  4980.7 1778.57
    4981 1779.07  4989.5 1779.89  5002.5 1779.83    5010 1780.11    5030 1780.17
    5040 1782.13    5050 1784.88    5060 1786.83    5070 1787.78    5080 1788.11
    5120 1788.42  5163.8 1789.17    5170 1789.44    5180 1789.51    5200 1789.94
#Mann= 5 ,-1 , 0
  4841.9    .035       0  4854.5     .07       0    4977     .05       0
    4981     .07       0  5163.8      .1       0
Bank Sta=4977,4981
XS Rating Curve= 0 ,0
Exp/Cntr=0.3,0.1

Type RM Length L Ch R = 1 ,232     ,0,0,0
BEGIN DESCRIPTION:
Stream0443 0.1
END DESCRIPTION:
XS GIS Cut Line= 4
      1888763.59     13951500.22      1888778.79      13951272.3
      1888633.39     13951131.25      1888208.99     13951070.62
#Sta/Elev= 30
  4632.9 1788.46  4698.3 1786.24    4777 1784.88  4848.6 1783.03    4883 1782.87
  4918.7 1782.27  4939.8 1780.64  4961.2 1776.42  4968.1 1773.91  4973.3  1773.9
  4973.6  1773.4  4977.1  1773.4  4977.3  1773.9  4989.5 1775.06  5024.7 1773.96
  5038.9 1777.82    5046 1779.04    5053 1778.84  5059.3  1779.6    5070 1779.78
  5075.1 1778.98  5101.8 1779.95  5140.7 1781.13  5145.8 1780.71  5211.4 1783.55
    5234  1783.9  5282.1 1786.67  5385.5 1786.76    5425 1787.35  5492.6 1788.41
#Mann= 7 ,-1 , 0
  4632.9     .07       0    4777    .035       0    4883     .07       0
  4973.3     .05       0  4977.3     .07       0  5101.8      .1       0
    5425    .035       0
Bank Sta=4973.3,4977.3
XS Rating Curve= 0 ,0
Exp/Cntr=0.3,0.1

Chan Stop Cuts=-1
Use User Specified Reach Order=0
Composite Channel Slope=5