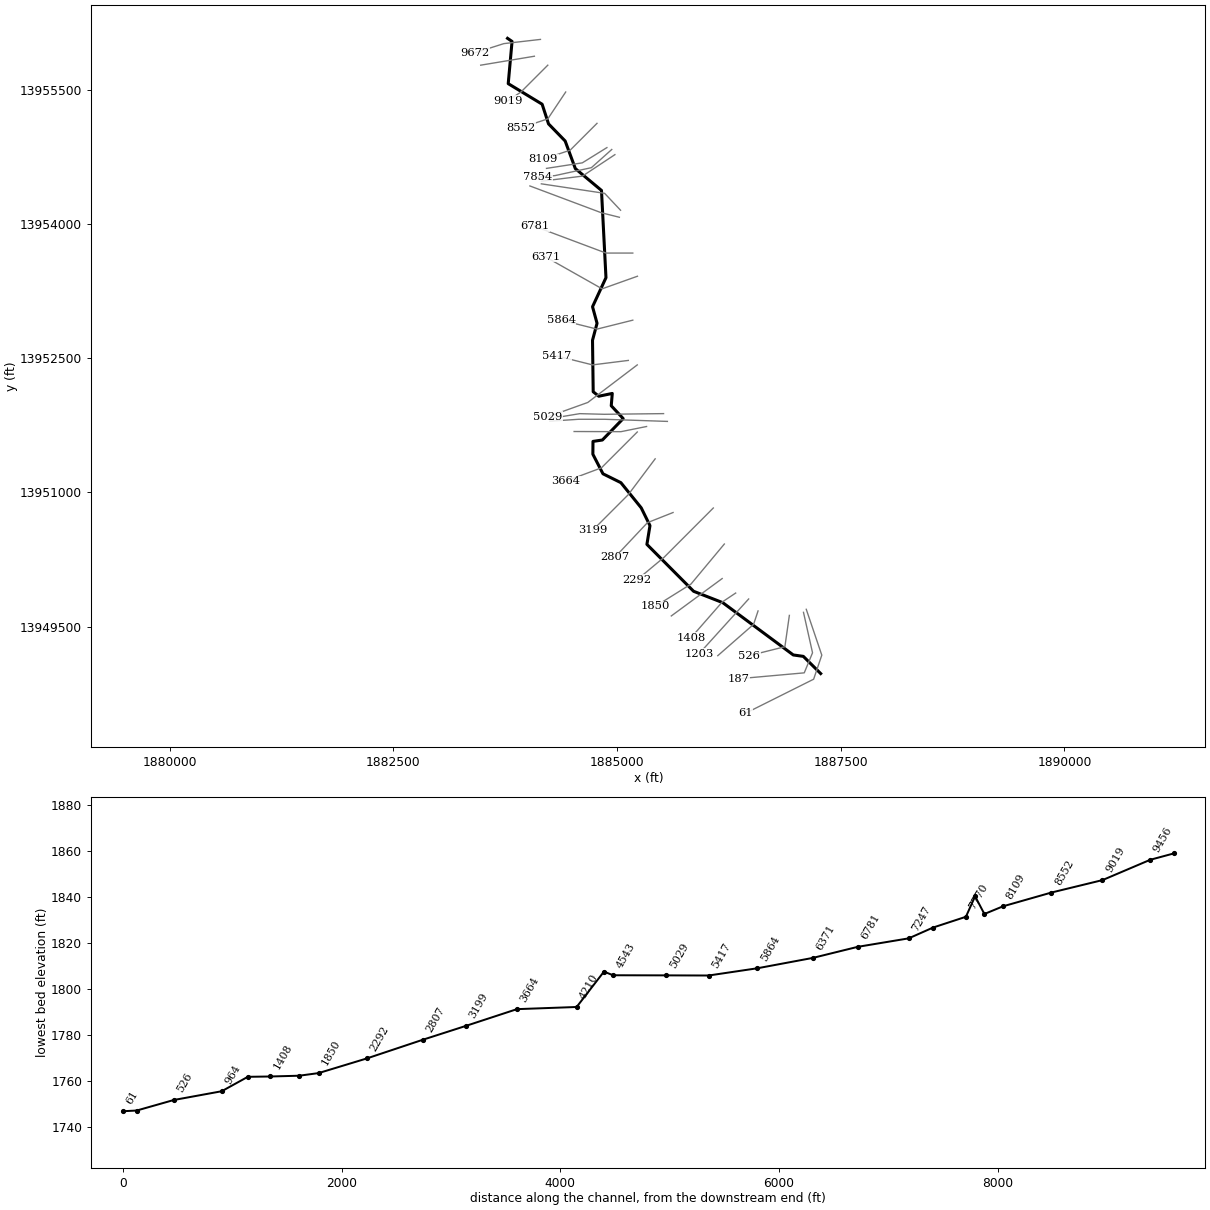
--- Stream0444.prj (project) ---

Proj Title=Stream0444 Base Level Engineering
Current Plan=p01
Default Exp/Contr=0.3,0.1
English Units
Geom File=g01
Flow File=f01
Plan File=p01
Y Axis Title=Elevation
X Axis Title(PF)=Main Channel Distance
X Axis Title(XS)=Station
BEGIN DESCRIPTION:
Stream0444
END DESCRIPTION:
DSS Export Rating Curves= 0
DSS Export Rating Curve Sorted= 0
DSS Export Volume Flow Curves= 0
DXF OffsetX= 0
DXF OffsetY= 0
DXF ScaleX= 1
DXF ScaleY= 10

--- Stream0444.p01 (plan) ---

Plan Title=Multiple Run
Short Identifier=Multiple
Geom File=g01
Flow File=f01
Subcritical Flow
K Sum by GR= 0
Std Step Tol= 0.01
Critical Tol= 0.01
Num of Std Step Trials= 20
Max Error Tol= 0.3
Flow Tol Ratio= 0.001
Split Flow NTrial= 30
Split Flow Tol= 0.02
Split Flow Ratio= 0.02
Log Output Level= 0
Friction Slope Method= 1
Unsteady Friction Slope Method= 2
Unsteady Bridges Friction Slope Method= 1
Parabolic Critical Depth
Global Vel Dist=  1 , 1 , 1
Global Log Level= 0
CheckData=True
Encroach Param= -1, 0, 0, 0
BEGIN DESCRIPTION:
Multiple Run
END DESCRIPTION:

--- Stream0444.f01 (steady flow) ---

Flow Title=Multiple
Number of Profiles=7
Profile Names=10-year,25-year,50-year,1pct_min,100-year,1pct_plu,500-year
River Rch & RM= Stream0444,Reach-1,9672
    1247    2156    3033    2064    4118    8217    7498
River Rch & RM= Stream0444,Reach-1,7470
    1615    2833    4024    2762    5510   10994   10209
River Rch & RM= Stream0444,Reach-1,5864
    2140    3797    5432    3748    7479   14922   14019
Boundary for River Rch & Prof#=Stream0444,Reach-1,1
Up Type=0
Dn Type=3
Dn Slope=0.005
Boundary for River Rch & Prof#=Stream0444,Reach-1,2
Up Type=0
Dn Type=3
Dn Slope=0.005
Boundary for River Rch & Prof#=Stream0444,Reach-1,3
Up Type=0
Dn Type=3
Dn Slope=0.005
Boundary for River Rch & Prof#=Stream0444,Reach-1,4
Up Type=0
Dn Type=3
Dn Slope=0.005
Boundary for River Rch & Prof#=Stream0444,Reach-1,5
Up Type=0
Dn Type=3
Dn Slope=0.005
Boundary for River Rch & Prof#=Stream0444,Reach-1,6
Up Type=0
Dn Type=3
Dn Slope=0.005
Boundary for River Rch & Prof#=Stream0444,Reach-1,7
Up Type=0
Dn Type=3
Dn Slope=0.005

--- Stream0444.g01 (geometry) ---

Geom Title=Existing Conditions
Program Version=4.10

River Reach=Stream0444      ,Reach-1
Reach XY= 30
        1883775.       13956075.      1883825.44     13956040.43
      1883782.69     13955568.52      1884161.74     13955338.65
      1884233.14     13955118.94      1884419.17      13954927.3
      1884532.86     13954618.83        1884825.       13954375.
      1884875.21     13953399.91        1884725.       13953075.
      1884775.47     13952890.16      1884724.77     13952700.07
      1884732.45     13952124.75      1884794.83      13952074.8
      1884945.63     13952105.87      1884934.15     13951968.27
      1885067.73     13951825.06      1884835.06     13951585.41
      1884730.03     13951569.92      1884728.74     13951426.56
      1884841.49     13951207.95      1885042.05     13951108.51
      1885269.17      13950827.3      1885366.96     13950628.32
      1885332.81     13950418.81      1885854.57     13949894.72
      1886181.16     13949767.12      1886968.84     13949182.88
      1887081.17     13949167.14        1887275.       13948975.

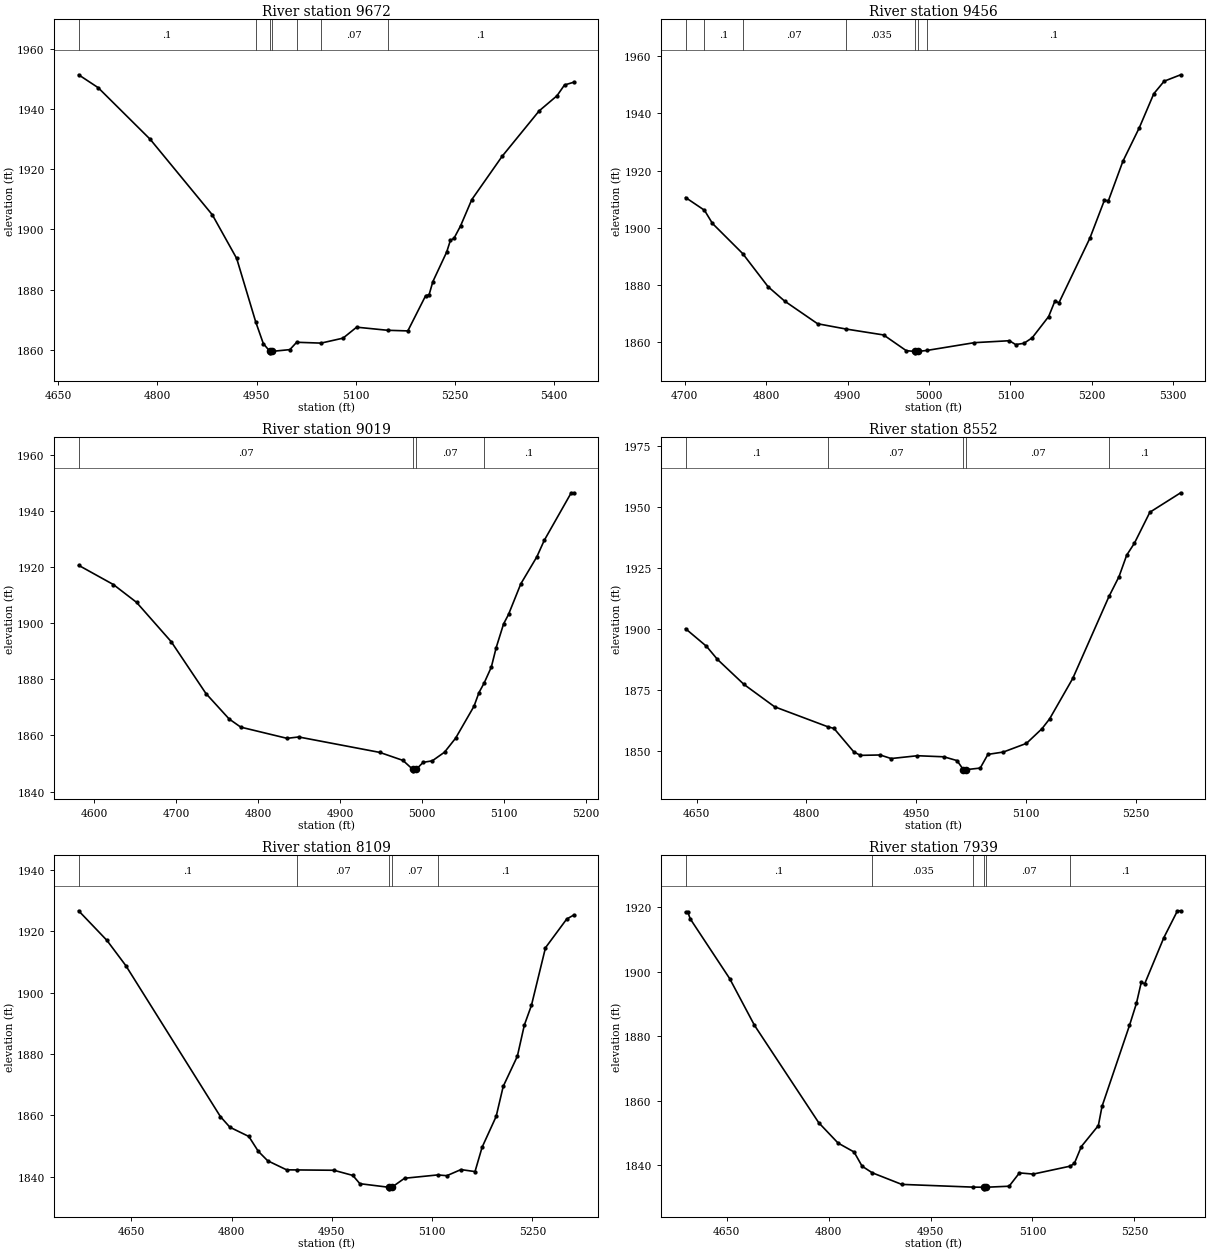
Type RM Length L Ch R = 1 ,9672    ,216,216,216
BEGIN DESCRIPTION:
Stream0444 21.0
END DESCRIPTION:
XS GIS Cut Line= 3
      1884142.72       13956063.      1883733.72     13956015.87
      1883411.75     13955913.69
#Sta/Elev= 30
  4680.6 1951.34  4710.2 1947.06    4789 1929.91  4883.1 1904.82  4919.9 1890.35
  4948.7  1869.3  4960.2 1862.09  4970.1 1859.51  4970.3 1859.01  4974.1 1859.51
  5000.4 1860.08  5010.7 1862.52  5047.6 1862.24  5080.9 1863.89  5101.5 1867.53
  5148.4  1866.5    5179 1866.29    5206    1878  5211.2 1878.31  5216.9 1882.67
  5237.8 1892.47  5243.5  1896.4  5248.8    1897  5258.8 1901.15  5275.8 1909.88
  5321.8 1924.28  5377.8 1939.35  5404.8 1944.37  5416.2 1947.96  5430.1 1948.86
#Mann= 7 ,-1 , 0
  4680.6      .1       0  4948.7     .07       0  4970.1     .05       0
  4974.1     .07       0  5010.7    .035       0  5047.6     .07       0
  5148.4      .1       0
Bank Sta=4970.1,4974.1
XS Rating Curve= 0 ,0
Exp/Cntr=0.3,0.1

Type RM Length L Ch R = 1 ,9456    ,437,437,437
BEGIN DESCRIPTION:
Stream0444 20.0
END DESCRIPTION:
XS GIS Cut Line= 3
      1884075.02       13955875.        1883775.       13955825.
        1883475.       13955775.
#Sta/Elev= 30
  4700.9 1910.58  4724.1 1906.13  4733.9 1901.52  4771.1 1890.96  4802.3 1879.37
  4822.6 1874.35  4863.1 1866.42    4898 1864.57  4944.2  1862.5  4972.1 1856.99
  4982.8 1856.74    4983 1856.24  4986.8 1856.74  4997.4 1857.08  5055.7  1859.8
  5098.8 1860.48  5106.4 1859.14  5116.6 1859.57  5126.7 1861.48    5147 1868.94
  5154.6 1874.29  5159.7 1873.78  5197.7 1896.38  5215.4 1909.55  5220.5 1909.53
  5238.2 1923.25  5258.5 1935.07  5276.2 1946.91  5288.9 1951.28  5309.2 1953.53
#Mann= 7 ,-1 , 0
  4700.9     .07       0  4724.1      .1       0  4771.1     .07       0
    4898    .035       0  4982.8     .05       0  4986.8    .035       0
  4997.4      .1       0
Bank Sta=4982.8,4986.8
XS Rating Curve= 0 ,0
Exp/Cntr=0.3,0.1

Type RM Length L Ch R = 1 ,9019    ,467,467,467
BEGIN DESCRIPTION:
Stream0444 19.0
END DESCRIPTION:
XS GIS Cut Line= 3
      1884224.99     13955774.99        1883925.       13955475.
      1883775.02     13955375.02
#Sta/Elev= 30
  4580.8 1920.63  4623.2 1913.78  4651.5 1907.44  4693.9  1893.4  4736.3 1874.93
  4764.6 1865.87  4778.8 1862.96  4835.3 1858.97  4849.5 1859.46  4948.5 1853.96
  4976.8 1851.11  4988.9 1847.89  4989.2 1847.39  4992.9 1847.89  5001.5 1850.42
  5012.6 1850.95  5027.6 1854.04  5041.1 1859.02  5063.6 1870.42  5069.6 1875.24
  5076.1 1878.77  5084.7 1884.33  5090.7 1891.33  5099.7 1899.75  5105.7  1903.1
  5120.7 1914.01  5140.3 1923.64  5149.3 1929.49  5182.3 1946.47  5185.3 1946.47
#Mann= 4 ,-1 , 0
  4580.8     .07       0  4988.9     .05       0  4992.9     .07       0
  5076.1      .1       0
Bank Sta=4988.9,4992.9
XS Rating Curve= 0 ,0
Exp/Cntr=0.3,0.1

Type RM Length L Ch R = 1 ,8552    ,443,443,443
BEGIN DESCRIPTION:
Stream0444 18.0
END DESCRIPTION:
XS GIS Cut Line= 3
      1884425.03     13955475.04        1884225.       13955175.
      1883925.03     13955075.01
#Sta/Elev= 30
  4634.8 1900.11  4663.4 1892.91  4678.4 1887.55  4714.5 1877.36  4756.5 1868.18
  4829.6 1859.97  4837.7 1859.32  4864.7 1849.76  4873.7 1848.31  4900.8 1848.47
  4915.8 1847.01  4951.8 1848.16  4987.9 1847.72  5005.9 1846.17  5014.5 1842.48
  5014.7 1841.98  5018.5 1842.48  5037.6 1843.11  5048.1 1848.71  5069.2 1849.67
  5100.8 1853.22  5121.9 1859.18  5132.4 1863.21  5164.1 1879.78  5213.6  1913.3
  5227.3  1921.4  5237.8 1930.18  5248.4  1935.1  5269.5 1947.75  5311.6 1955.71
#Mann= 5 ,-1 , 0
  4634.8      .1       0  4829.6     .07       0  5014.5     .05       0
  5018.5     .07       0  5213.6      .1       0
Bank Sta=5014.5,5018.5
XS Rating Curve= 0 ,0
Exp/Cntr=0.3,0.1

Type RM Length L Ch R = 1 ,8109    ,170,170,170
BEGIN DESCRIPTION:
Stream0444 17.0
END DESCRIPTION:
XS GIS Cut Line= 3
        1884775.       13955125.        1884475.       13954825.
        1884175.       13954725.
#Sta/Elev= 30
  4571.2 1926.71  4613.6 1917.04  4641.9 1908.79  4783.3 1859.55  4797.5 1856.08
  4825.8 1853.07  4839.9 1848.24    4854 1845.14  4882.3 1842.18  4897.9 1842.15
    4953 1842.04  4981.3 1840.36  4991.9 1837.66  5035.6 1836.48  5035.9 1835.98
  5039.6 1836.48  5058.7 1839.43  5108.3 1840.52    5122 1840.27    5143 1842.26
  5164.1 1841.61  5174.7 1849.55  5195.7 1859.59  5206.3 1869.42  5227.4 1879.22
  5237.9 1889.43  5248.5 1895.84  5269.5 1914.65  5301.2    1924  5311.7 1925.31
#Mann= 5 ,-1 , 0
  4571.2      .1       0  4897.9     .07       0  5035.6     .05       0
  5039.6     .07       0  5108.3      .1       0
Bank Sta=5035.6,5039.6
XS Rating Curve= 0 ,0
Exp/Cntr=0.3,0.1

Type RM Length L Ch R = 1 ,7939    ,85,85,85
BEGIN DESCRIPTION:
Stream0444 16.1
END DESCRIPTION:
XS GIS Cut Line= 3
      1884885.71     13954853.74      1884610.87      13954683.3
      1884210.62     13954621.47
#Sta/Elev= 30
  4589.6 1918.38  4592.9 1918.38  4596.5 1916.31  4654.4 1897.83    4691 1883.31
  4785.5 1853.14    4814 1846.82  4837.5 1844.06  4849.3 1839.66  4864.2 1837.62
  4907.6 1834.02  5012.8 1833.17  5028.2 1833.14  5028.5 1832.64  5032.2 1833.14
  5065.6 1833.45  5080.8 1837.58  5101.1 1837.21  5155.9 1839.69  5161.8 1840.62
  5171.9 1845.76  5196.9 1852.25  5202.3 1858.19  5242.7 1883.29  5252.9 1890.11
    5260 1896.62  5265.1  1896.2  5293.3 1910.51  5313.3 1918.82    5318 1918.82
#Mann= 6 ,-1 , 0
  4589.6      .1       0  4864.2    .035       0  5012.8     .07       0
  5028.2    .035       0  5032.2     .07       0  5155.9      .1       0
Bank Sta=5028.2,5032.2
XS Rating Curve= 0 ,0
Exp/Cntr=0.3,0.1

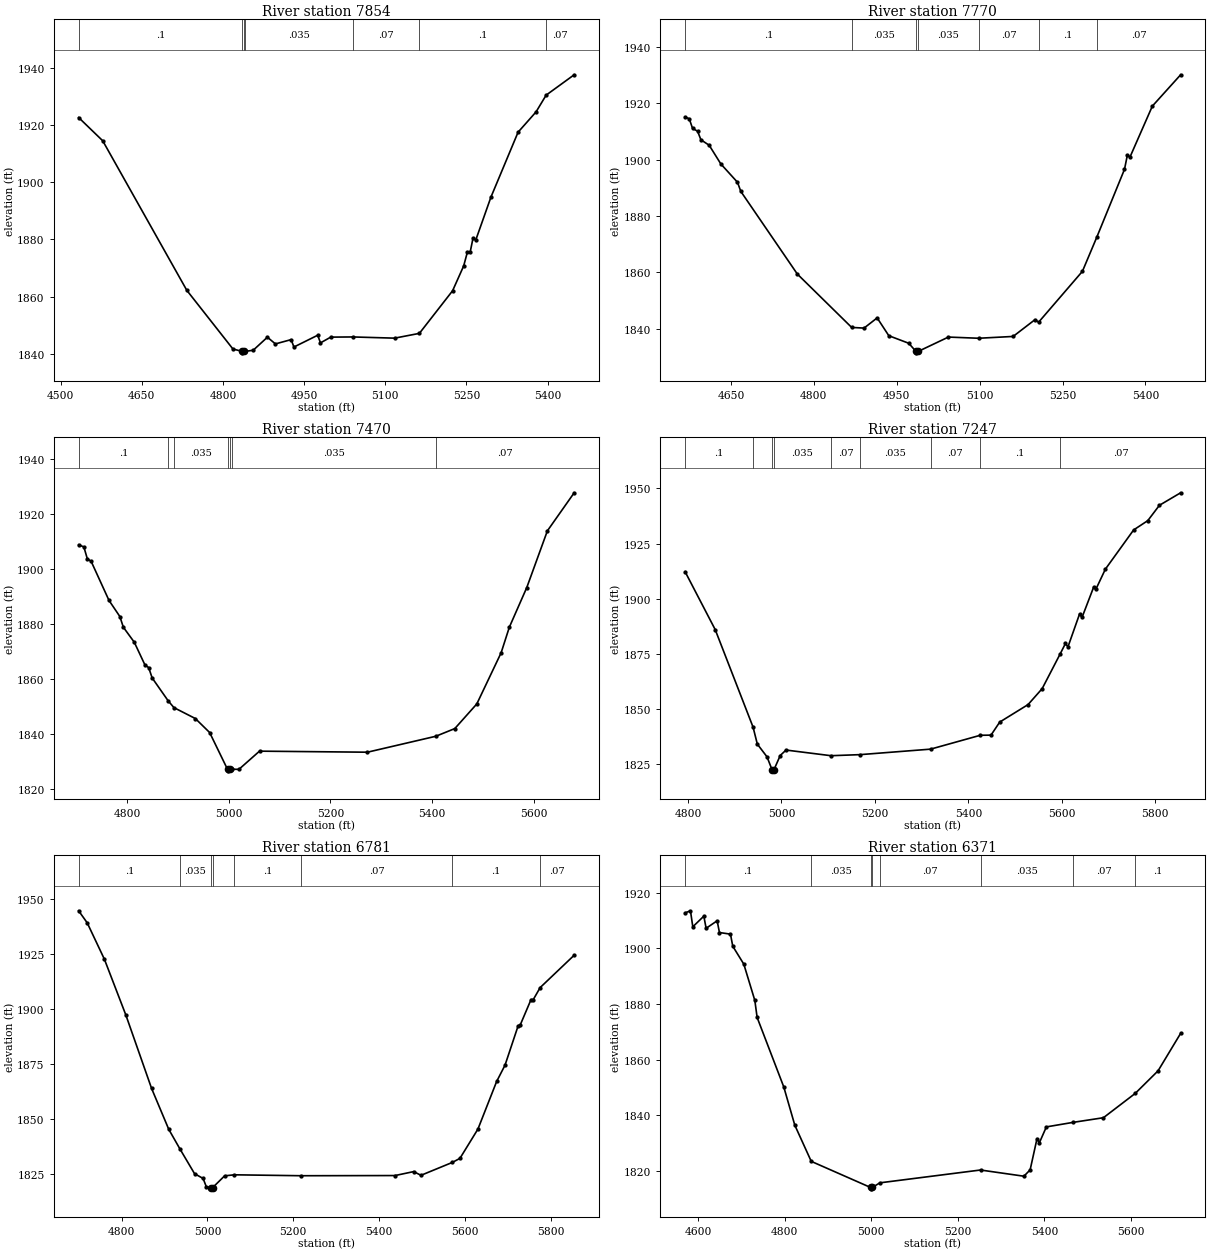
Type RM Length L Ch R = 1 ,7854    ,84,84,84
BEGIN DESCRIPTION:
Stream0444 16.3
END DESCRIPTION:
XS GIS Cut Line= 4
      1884939.83     13954832.58      1884712.41     13954629.47
      1884306.16     13954540.93      1884111.74     13954523.57
#Sta/Elev= 30
  4533.3 1922.56  4577.8 1914.44  4733.3 1862.18  4818.5  1841.7  4835.8 1840.86
  4836.1 1840.36  4839.8 1840.86  4841.4 1840.87    4856 1841.27  4882.2 1845.82
    4897 1843.48  4926.1 1844.98  4931.2 1842.39  4975.2 1846.51  4980.3 1843.84
  4999.3 1845.85  5040.4 1845.91  5117.3 1845.49  5163.1 1847.16  5224.5 1862.05
    5245 1870.73    5252 1875.67  5257.1 1875.67  5262.3 1880.47  5267.3 1879.75
  5295.3 1894.73  5345.5 1917.43  5378.8 1924.54  5397.4 1930.38  5449.2 1937.49
#Mann= 7 ,-1 , 0
  4533.3      .1       0  4835.8    .035       0  4839.8      .1       0
  4841.4    .035       0  5040.4     .07       0  5163.1      .1       0
  5397.4     .07       0
Bank Sta=4835.8,4839.8
XS Rating Curve= 0 ,0
Exp/Cntr=0.3,0.1

Type RM Length L Ch R = 1 ,7770    ,300,300,300
BEGIN DESCRIPTION:
Stream0444 16.0
END DESCRIPTION:
XS GIS Cut Line= 3
        1884975.       13954775.      1884612.34     13954534.95
      1884154.16     13954478.14
#Sta/Elev= 30
    4567 1915.16  4574.5 1914.56  4580.5 1911.13  4589.6 1910.13  4595.6 1907.09
  4610.6 1905.14  4631.7  1898.5  4661.8    1892  4667.8 1888.76  4770.1  1859.4
  4868.4 1840.45  4890.8 1840.22  4914.5 1843.84  4935.6 1837.51  4971.7 1834.83
  4984.7 1831.93    4985 1831.43  4988.7 1831.93  5043.4 1837.03    5098 1836.61
  5160.5 1837.25  5200.2 1843.23  5206.6  1842.3  5285.9 1860.38  5311.9  1872.5
    5362 1896.59  5367.1 1901.52  5372.1 1901.02  5412.4 1919.04  5463.6 1930.17
#Mann= 7 ,-1 , 0
    4567      .1       0  4868.4    .035       0  4984.7    .035       0
  4988.7    .035       0    5098     .07       0  5206.6      .1       0
  5311.9     .07       0
Bank Sta=4984.7,4988.7
XS Rating Curve= 0 ,0
Exp/Cntr=0.3,0.1

Type RM Length L Ch R = 1 ,7470    ,223,223,223
BEGIN DESCRIPTION:
Stream0444 15.2
END DESCRIPTION:
XS GIS Cut Line= 3
      1885038.21     13954153.67      1884860.27     13954342.47
      1884152.85      13954448.8
#Sta/Elev= 30
  4704.9 1908.75  4715.2 1907.97  4722.1 1903.59  4729.4 1902.79  4764.6 1888.58
    4786 1882.72  4792.9 1878.83  4814.4 1873.39  4835.4 1865.14  4842.7  1864.2
  4849.5 1860.46  4881.1 1852.13  4892.4 1849.68  4934.5 1845.72  4962.6 1840.65
  4997.9 1827.25  4998.2 1826.75    5002 1827.25  5006.7 1827.34  5020.2 1827.29
  5060.7 1833.89    5273 1833.51  5407.5 1839.29  5444.9 1842.08  5488.2 1851.03
    5536 1869.57  5552.2 1878.87  5586.5 1893.25    5627  1913.8  5679.7 1927.61
#Mann= 7 ,-1 , 0
  4704.9      .1       0  4881.1    .035       0  4892.4    .035       0
  4997.9    .035       0    5002    .035       0  5006.7    .035       0
  5407.5     .07       0
Bank Sta=4997.9,5002
XS Rating Curve= 0 ,0
Exp/Cntr=0.3,0.1

Type RM Length L Ch R = 1 ,7247    ,466,466,466
BEGIN DESCRIPTION:
Stream0444 15.0
END DESCRIPTION:
XS GIS Cut Line= 3
      1885025.03     13954074.99        1884825.       13954125.
      1884024.99       13954425.
#Sta/Elev= 30
  4793.8 1912.29  4858.3 1886.02  4939.3 1841.83  4948.4 1834.15  4969.1 1828.39
  4979.9 1822.54  4980.1 1822.04    4984 1822.54  4997.4 1828.99  5009.8 1831.46
    5106  1828.9  5168.2 1829.38  5319.1 1831.87  5425.7 1838.16  5448.5 1838.22
  5467.2 1844.14  5527.8 1852.06    5558 1859.28  5596.8 1875.13  5607.9 1879.77
  5613.2  1878.2  5638.1 1893.15  5643.5 1891.65  5668.4  1905.4  5673.7 1904.65
  5693.3 1913.44  5753.8 1931.22  5784.1 1935.44    5809 1942.39  5854.4 1948.06
#Mann= 9 ,-1 , 0
  4793.8      .1       0  4939.3    .035       0  4979.9    .035       0
    4984    .035       0    5106     .07       0  5168.2    .035       0
  5319.1     .07       0  5425.7      .1       0  5596.8     .07       0
Bank Sta=4979.9,4984
XS Rating Curve= 0 ,0
Exp/Cntr=0.3,0.1

Type RM Length L Ch R = 1 ,6781    ,410,410,410
BEGIN DESCRIPTION:
Stream0444 14.0
END DESCRIPTION:
XS GIS Cut Line= 3
      1885175.03       13953675.        1884875.       13953675.
      1884075.03     13953974.99
#Sta/Elev= 30
    4700 1944.78    4720 1939.29    4760 1922.76    4810 1897.39    4870 1863.98
    4910 1845.39  4936.4 1836.35    4970 1825.25    4990 1823.06  4997.5 1819.27
  5007.8 1818.85    5008 1818.35  5011.9 1818.85  5040.1 1824.26    5063 1824.73
  5218.5 1824.31    5437 1824.39  5480.6 1826.19  5497.5  1824.5  5570.8 1830.38
  5588.3 1832.21  5630.2 1845.52  5673.8 1867.17  5693.3 1874.58  5723.6 1892.32
  5728.9 1892.93  5753.9 1904.41  5759.2 1904.43  5775.2 1909.87  5854.4 1924.57
#Mann= 8 ,-1 , 0
    4700      .1       0  4936.4    .035       0  5007.8    .035       0
  5011.9    .035       0    5063      .1       0  5218.5     .07       0
  5570.8      .1       0  5775.2     .07       0
Bank Sta=5007.8,5011.9
XS Rating Curve= 0 ,0
Exp/Cntr=0.3,0.1

Type RM Length L Ch R = 1 ,6371    ,507,507,507
BEGIN DESCRIPTION:
Stream0444 13.0
END DESCRIPTION:
XS GIS Cut Line= 3
       1885226.8     13953415.93      1884832.16     13953275.23
      1884199.56     13953632.52
#Sta/Elev= 30
  4569.6 1912.77    4582 1913.52  4587.4 1907.76  4612.9 1911.58  4618.2 1907.22
  4643.7 1909.92    4649  1905.7  4674.5 1905.12  4679.8 1900.77  4705.3 1894.34
  4730.8 1881.28  4736.1 1875.17  4797.7 1850.18  4823.2 1836.43  4861.2 1823.42
  4998.3 1814.04  4998.6 1813.54  5002.5 1814.04  5019.8  1815.7  5252.5 1820.31
  5352.8 1818.08  5367.2 1820.37  5383.1  1831.6  5388.8 1830.19  5404.7 1835.81
  5467.2 1837.46  5536.6 1839.11  5610.1 1847.85  5662.9 1855.97  5715.1 1869.44
#Mann= 8 ,-1 , 0
  4569.6      .1       0  4861.2    .035       0  4998.3    .035       0
  5002.5    .035       0  5019.8     .07       0  5252.5    .035       0
  5467.2     .07       0  5610.1      .1       0
Bank Sta=4998.3,5002.5
XS Rating Curve= 0 ,0
Exp/Cntr=0.3,0.1

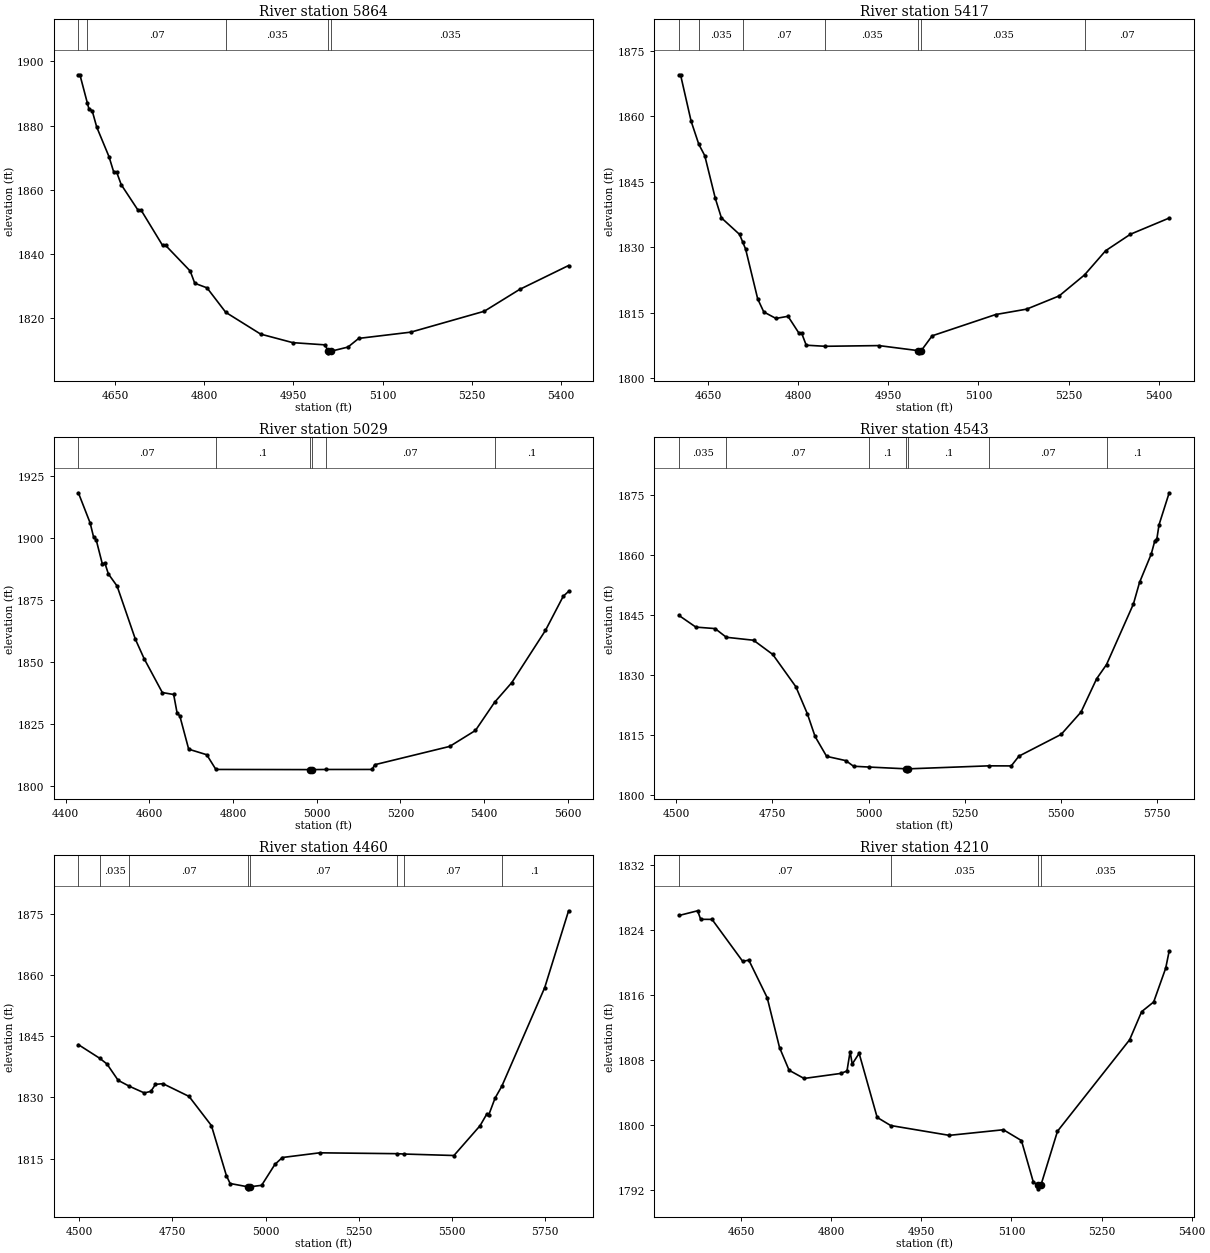
Type RM Length L Ch R = 1 ,5864    ,447,447,447
BEGIN DESCRIPTION:
Stream0444 12.0
END DESCRIPTION:
XS GIS Cut Line= 3
      1885174.98     13952924.99        1884775.       13952825.
        1884375.       13952925.
#Sta/Elev= 30
  4588.2 1895.84  4590.8 1895.84  4603.5 1886.89  4606.2 1885.04  4611.4 1884.64
  4619.1  1879.5  4639.7 1870.29  4647.4 1865.64  4652.6 1865.44  4660.3 1861.53
  4688.7 1853.53  4693.8 1853.56  4729.9 1842.55  4735.1 1842.55  4776.3 1834.57
    4784 1830.75  4804.6 1829.32  4836.1 1821.68  4894.8 1814.88  4948.9 1812.21
  5003.1 1811.52  5008.4 1809.53  5008.8 1809.03  5013.1 1809.53  5041.7 1810.83
  5059.8 1813.54  5147.4 1815.49  5271.1 1822.02  5330.3 1828.81  5412.8 1836.29
#Mann= 5 ,-1 , 0
  4588.2      .1       0  4603.5     .07       0  4836.1    .035       0
  5008.4    .035       0  5013.1    .035       0
Bank Sta=5008.4,5013.1
XS Rating Curve= 0 ,0
Exp/Cntr=0.3,0.1

Type RM Length L Ch R = 1 ,5417    ,388,388,388
BEGIN DESCRIPTION:
Stream0444 11.0
END DESCRIPTION:
XS GIS Cut Line= 3
      1885125.03       13952475.        1884725.       13952425.
      1884324.96     13952525.01
#Sta/Elev= 30
  4601.8 1869.55  4604.4 1869.55    4622 1858.92  4634.8 1853.63  4644.7 1851.03
  4662.3 1841.22  4672.4 1836.78  4702.6 1832.99    4708 1831.19  4712.7 1829.62
  4732.8 1818.21  4742.9 1815.23  4763.1 1813.75  4783.2 1814.24  4800.9 1810.48
  4805.9 1810.36  4813.5 1807.62  4844.9 1807.37  4934.4 1807.53    5000 1806.37
  5000.4 1805.87  5004.8 1806.37    5023 1809.77  5128.6 1814.64  5180.2 1815.88
  5234.3 1818.91  5276.5 1823.72  5311.6 1829.26  5352.8 1833.03  5417.3 1836.74
#Mann= 7 ,-1 , 0
  4601.8     .07       0  4634.8    .035       0    4708     .07       0
  4844.9    .035       0    5000    .035       0  5004.8    .035       0
  5276.5     .07       0
Bank Sta=5000,5004.8
XS Rating Curve= 0 ,0
Exp/Cntr=0.3,0.1

Type RM Length L Ch R = 1 ,5029    ,486,486,486
BEGIN DESCRIPTION:
Stream0444 10.0
END DESCRIPTION:
XS GIS Cut Line= 3
      1885224.97     13952424.97      1884672.07     13952005.12
      1884223.09     13951843.86
#Sta/Elev= 30
  4430.7 1918.15  4458.8 1905.98    4467 1900.34  4473.3 1899.15  4487.8 1889.54
  4494.1 1889.75  4502.4  1885.4  4523.2 1880.51  4566.9 1859.05  4587.7 1851.25
  4631.3 1837.53  4658.4 1836.74  4666.7  1829.2    4673 1828.15  4694.3 1814.67
  4737.4 1812.43  4759.3 1806.49  4984.5 1806.43  4984.9 1805.93  4989.5 1806.43
  5021.7 1806.48  5132.5 1806.49  5138.9  1808.4    5318 1815.79  5379.5 1822.23
  5425.2 1833.59  5466.3 1841.54  5546.8 1862.62  5589.3  1876.4    5602 1878.34
#Mann= 6 ,-1 , 0
  4430.7     .07       0  4759.3      .1       0  4984.5     .05       0
  4989.5      .1       0  5021.7     .07       0  5425.2      .1       0
Bank Sta=4984.5,4989.5
XS Rating Curve= 0 ,0
Exp/Cntr=0.3,0.1

Type RM Length L Ch R = 1 ,4543    ,83,83,83
BEGIN DESCRIPTION:
Mapping XS 1ea2ce37
END DESCRIPTION:
XS GIS Cut Line= 4
      1885518.91     13951880.44      1884855.69     13951872.77
      1884582.55     13951880.07      1884248.93     13951824.64
#Sta/Elev= 30
  4506.8 1844.79  4550.7 1841.88  4600.7 1841.51  4629.9 1839.34  4700.7  1838.6
  4750.7 1835.05  4810.7 1826.99  4840.7 1820.22  4860.7 1814.56  4890.7  1809.6
  4940.7 1808.53  4960.7 1807.13  5001.9 1806.92  5098.2 1806.48  5098.6 1805.98
  5103.3 1806.48  5312.8 1807.23  5370.8 1807.21  5390.8 1809.65  5500.7 1815.09
  5552.3 1820.67  5592.9 1828.99  5618.5 1832.51  5688.5 1847.66  5704.4 1853.04
  5734.8 1860.12  5744.3 1863.48  5749.4 1863.88  5755.1 1867.44  5781.5 1875.43
#Mann= 7 ,-1 , 0
  4506.8    .035       0  4629.9     .07       0  5001.9      .1       0
  5098.2     .05       0  5103.3      .1       0  5312.8     .07       0
  5618.5      .1       0
Bank Sta=5098.2,5103.3
XS Rating Curve= 0 ,0
Exp/Cntr=0.3,0.1

Type RM Length L Ch R = 1 ,4460    ,250,250,250
BEGIN DESCRIPTION:
Stream0444 9.0
END DESCRIPTION:
XS GIS Cut Line= 4
      1885561.64     13951793.29      1884860.72     13951817.16
      1884569.93     13951817.16      1884248.26     13951795.58
#Sta/Elev= 30
  4498.2 1842.96  4555.6  1839.6  4574.9 1838.21  4604.9  1834.2  4635.3 1832.73
  4674.9 1831.11  4692.6 1831.49    4705 1833.21    4725 1833.38    4795 1830.25
    4855 1823.09  4895.1 1810.83  4905.1 1808.88  4952.5 1808.07  4952.9 1807.57
  4957.6 1808.07  4989.6 1808.43  5025.1 1813.55  5045.2 1815.26  5145.2 1816.41
  5351.6  1816.2  5372.3 1816.11  5505.3 1815.75  5575.4 1823.07  5593.9 1826.01
  5598.9 1825.77  5615.5 1829.82  5633.7 1832.76  5748.7 1856.95  5812.7 1875.81
#Mann= 8 ,-1 , 0
  4498.2     .07       0  4555.6    .035       0  4635.3     .07       0
  4952.5     .05       0  4957.6     .07       0  5351.6    .035       0
  5372.3     .07       0  5633.7      .1       0
Bank Sta=4952.5,4957.6
XS Rating Curve= 0 ,0
Exp/Cntr=0.3,0.1

Type RM Length L Ch R = 1 ,4210    ,546,546,546
BEGIN DESCRIPTION:
Mapping XS b742710e
END DESCRIPTION:
XS GIS Cut Line= 3
      1885328.94     13951736.43      1885043.08     13951678.64
      1884519.22     13951680.34
#Sta/Elev= 30
    4547  1825.8    4578 1826.38  4583.1 1825.33    4602 1825.32    4653 1820.16
  4663.2 1820.31  4693.8 1815.68  4714.3 1809.55  4730.2 1806.76  4755.1 1805.75
  4816.3 1806.37  4826.5 1806.67  4831.7 1809.06  4835.2 1807.52  4846.7 1808.84
  4876.7 1800.96  4899.2 1799.96  4996.7 1798.75  5086.7 1799.44  5116.7 1798.11
  5136.7 1792.95  5144.2 1792.67  5144.6 1792.17  5149.3 1792.67  5176.7 1799.26
  5296.7 1810.51  5316.7 1813.97  5336.7 1815.16  5356.7 1819.32  5362.5 1821.43
#Mann= 4 ,-1 , 0
    4547     .07       0  4899.2    .035       0  5144.2    .035       0
  5149.3    .035       0
Bank Sta=5144.2,5149.3
XS Rating Curve= 0 ,0
Exp/Cntr=0.3,0.1

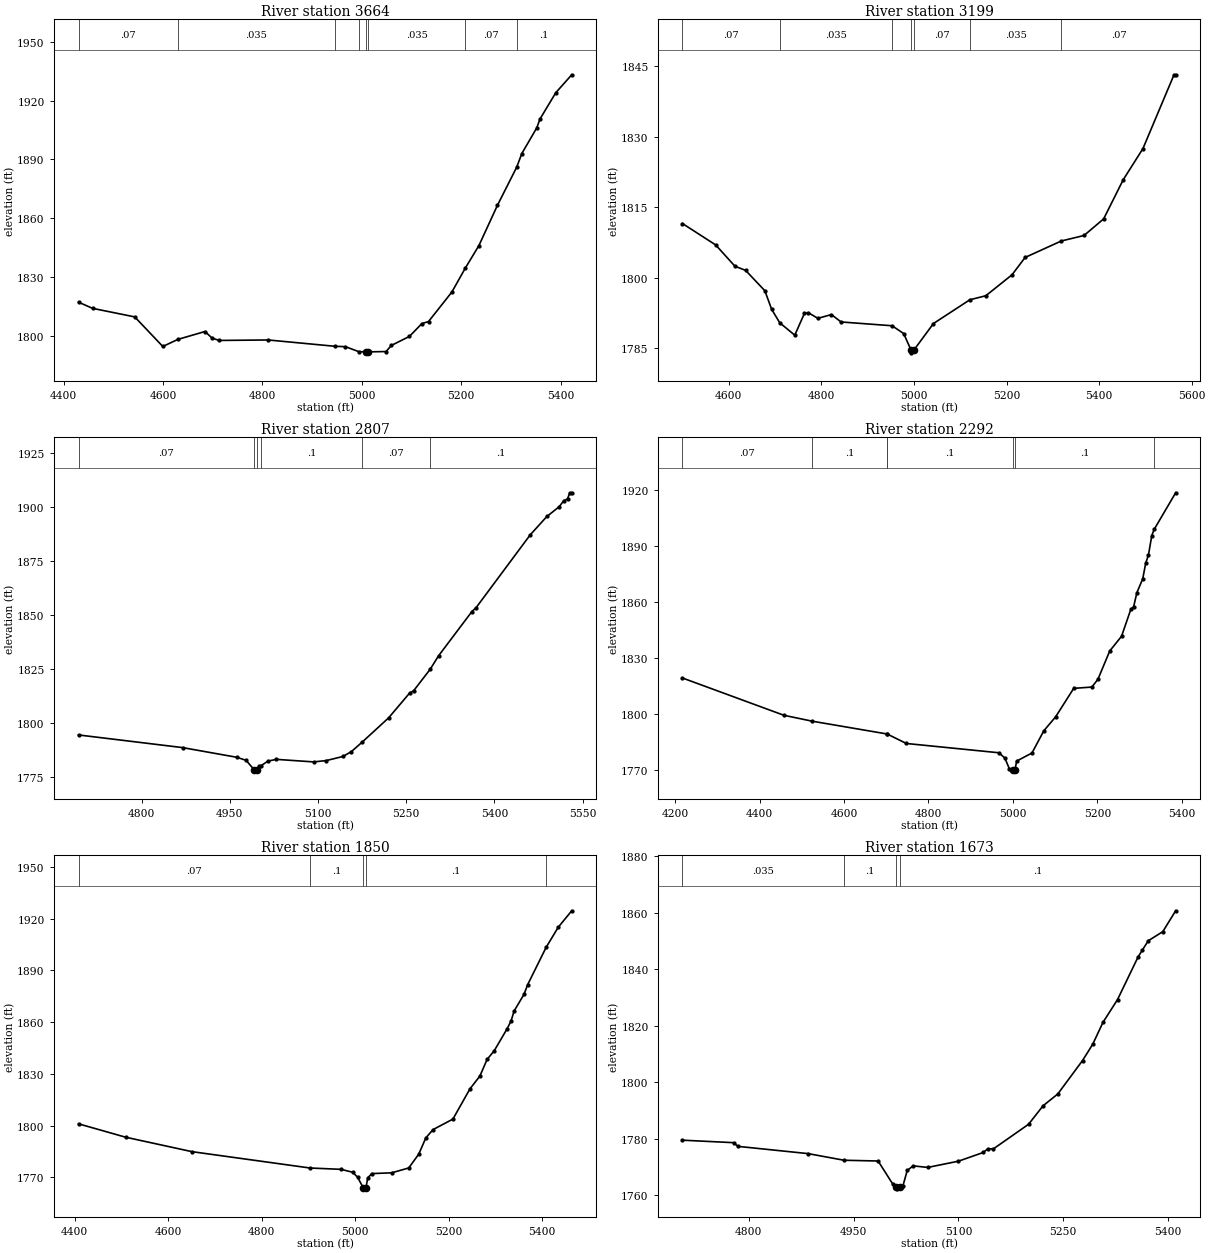
Type RM Length L Ch R = 1 ,3664    ,465,465,465
BEGIN DESCRIPTION:
Stream0444 8.0
END DESCRIPTION:
XS GIS Cut Line= 3
      1885225.03     13951675.03        1884825.       13951275.
      1884425.03     13951125.01
#Sta/Elev= 30
  4429.7  1817.1    4458 1813.95  4542.9 1809.58  4599.4 1794.47  4629.7 1798.09
  4684.3 1802.12  4698.4  1798.8  4712.6 1797.56  4811.6  1797.8  4946.3 1794.57
  4967.1 1794.38  4993.7 1791.85    5008 1791.73  5008.4 1791.23  5013.1 1791.73
  5048.8 1791.89  5059.5 1795.01    5096 1799.64  5120.9 1806.16  5134.3  1807.2
  5181.4 1822.31  5207.9 1834.31  5235.7 1845.97  5273.1 1866.59  5311.9 1886.07
  5322.1 1892.99  5352.3 1906.14  5358.5 1910.55  5390.6 1924.08  5422.6 1933.21
#Mann= 8 ,-1 , 0
  4429.7     .07       0  4629.7    .035       0  4946.3     .07       0
  4993.7    .035       0    5008    .035       0  5013.1    .035       0
  5207.9     .07       0  5311.9      .1       0
Bank Sta=5008,5013.1
XS Rating Curve= 0 ,0
Exp/Cntr=0.3,0.1

Type RM Length L Ch R = 1 ,3199    ,392,392,392
BEGIN DESCRIPTION:
Stream0444 7.0
END DESCRIPTION:
XS GIS Cut Line= 3
      1885424.99     13951374.98        1885125.       13950975.
      1884724.98     13950574.98
#Sta/Elev= 30
  4499.8 1811.53  4571.7 1806.96  4613.3 1802.42  4636.2 1801.55  4677.9  1797.2
  4692.5 1793.25  4710.1 1790.37  4742.5 1787.73  4763.3 1792.37  4771.7 1792.52
  4792.5 1791.32  4821.7 1792.13  4842.5 1790.55  4952.9 1789.74  4977.9 1788.07
  4994.1 1784.47  4994.5 1783.97  4999.2 1784.47  5042.2 1790.22  5120.8 1795.28
  5155.3 1796.14  5211.9  1800.6  5240.2  1804.3  5318.5 1807.81  5367.5 1808.98
  5409.9 1812.52  5452.3 1820.88  5494.8  1827.5  5561.9 1843.23  5565.5 1843.23
#Mann= 7 ,-1 , 0
  4499.8     .07       0  4710.1    .035       0  4952.9     .07       0
  4994.1     .05       0  4999.2     .07       0  5120.8    .035       0
  5318.5     .07       0
Bank Sta=4994.1,4999.2
XS Rating Curve= 0 ,0
Exp/Cntr=0.3,0.1

Type RM Length L Ch R = 1 ,2807    ,515,515,515
BEGIN DESCRIPTION:
Stream0444 6.0
END DESCRIPTION:
XS GIS Cut Line= 3
      1885625.05     13950775.02      1885338.63     13950661.38
      1884975.01     13950275.01
#Sta/Elev= 30
  4692.8 1794.57  4869.7 1788.72  4961.8 1784.25  4977.8 1782.84  4991.4 1778.47
  4991.8 1777.97  4996.8 1778.47  5000.2  1780.2  5003.5  1780.4    5015 1782.48
  5029.2 1783.28  5092.7  1782.1  5114.2 1782.73  5142.5 1784.62  5156.7 1786.84
  5175.2 1791.26  5220.2  1802.5  5255.8 1813.93  5262.7 1815.03  5290.8 1824.95
  5305.1  1831.2  5361.8 1851.67  5368.7 1853.38  5460.9 1887.12  5489.2 1895.62
  5510.3 1900.15  5517.6 1902.84  5524.4  1903.8  5528.1 1906.59  5531.5 1906.59
#Mann= 6 ,-1 , 0
  4692.8     .07       0  4991.4     .05       0  4996.8     .07       0
  5003.5      .1       0  5175.2     .07       0  5290.8      .1       0
Bank Sta=4991.4,4996.8
XS Rating Curve= 0 ,0
Exp/Cntr=0.3,0.1

Type RM Length L Ch R = 1 ,2292    ,442,442,442
BEGIN DESCRIPTION:
Stream0444 5.0
END DESCRIPTION:
XS GIS Cut Line= 3
      1886074.78     13950825.48        1885525.       13950275.
      1885225.01     13950025.01
#Sta/Elev= 30
  4217.1 1819.45  4457.7 1799.49  4524.6 1796.34  4700.7 1789.55  4701.9 1789.51
  4747.6 1784.42  4966.8 1779.46    4981 1776.62  4991.6 1770.87  4999.5 1770.29
    5000 1769.79    5005 1770.29  5008.8    1775  5045.2 1779.34  5073.2  1791.2
  5101.2 1798.67  5144.1 1813.91  5187.1  1814.6  5201.4 1818.74  5229.4 1833.89
  5257.4 1841.77  5279.5 1856.24    5286 1857.53  5293.8 1865.15  5307.5 1872.41
  5314.7 1880.93  5321.2 1885.29    5329 1895.61  5334.7 1898.94  5385.6 1918.51
#Mann= 7 ,-1 , 0
  4217.1     .07       0  4524.6      .1       0  4700.7     .07       0
  4701.9      .1       0  4999.5     .05       0    5005      .1       0
  5334.7     .07       0
Bank Sta=4999.5,5005
XS Rating Curve= 0 ,0
Exp/Cntr=0.3,0.1

Type RM Length L Ch R = 1 ,1850    ,177,177,177
BEGIN DESCRIPTION:
Stream0444 4.0
END DESCRIPTION:
XS GIS Cut Line= 3
      1886198.16     13950422.92        1885825.       13949975.
      1885424.99       13949725.
#Sta/Elev= 30
  4408.5 1801.08  4509.2 1793.33  4651.1 1784.95  4903.7 1775.47    4970  1774.7
  4994.4 1773.03  5005.1 1770.23  5017.6  1763.9    5018  1763.4  5023.1  1763.9
  5026.9 1769.73  5035.7 1772.23  5078.2 1772.69  5114.7  1775.5    5136 1783.51
  5151.3 1792.97  5166.6 1797.72  5209.1 1803.82  5245.6 1821.36  5266.8 1828.75
  5282.2 1838.42  5297.5 1843.44  5324.6 1855.97  5333.5 1860.72    5340 1866.47
  5361.2 1876.14  5368.9 1881.71  5408.6 1903.43  5434.3 1914.99  5463.2 1924.56
#Mann= 5 ,-1 , 0
  4408.5     .07       0  4903.7      .1       0  5017.6     .05       0
  5023.1      .1       0  5408.6     .07       0
Bank Sta=5017.6,5023.1
XS Rating Curve= 0 ,0
Exp/Cntr=0.3,0.1

Type RM Length L Ch R = 1 ,1673    ,265,265,265
BEGIN DESCRIPTION:
Mapping XS e5c5eccd
END DESCRIPTION:
XS GIS Cut Line= 2
      1886174.07     13950036.97      1885605.35     13949618.99
#Sta/Elev= 30
  4705.1 1779.48  4778.3  1778.6  4784.5 1777.29  4884.8 1774.73  4936.3 1772.38
  4985.1 1772.11    5006 1763.97  5011.4 1762.76  5011.9 1762.26    5017 1762.76
  5020.6  1763.3  5026.8 1768.78  5035.3 1770.39  5056.1 1769.84  5100.1 1772.05
  5135.6 1775.13  5141.8 1776.39  5150.2 1776.43  5200.4 1785.11  5221.2 1791.67
  5242.1  1795.8  5277.6 1807.66  5292.2 1813.42  5306.9 1821.18  5327.7 1829.24
    5357 1844.27  5363.2 1846.75  5371.7 1850.06  5392.5 1853.29  5410.9 1860.67
#Mann= 4 ,-1 , 0
  4705.1    .035       0  4936.3      .1       0  5011.4     .05       0
    5017      .1       0
Bank Sta=5011.4,5017
XS Rating Curve= 0 ,0
Exp/Cntr=0.3,0.1

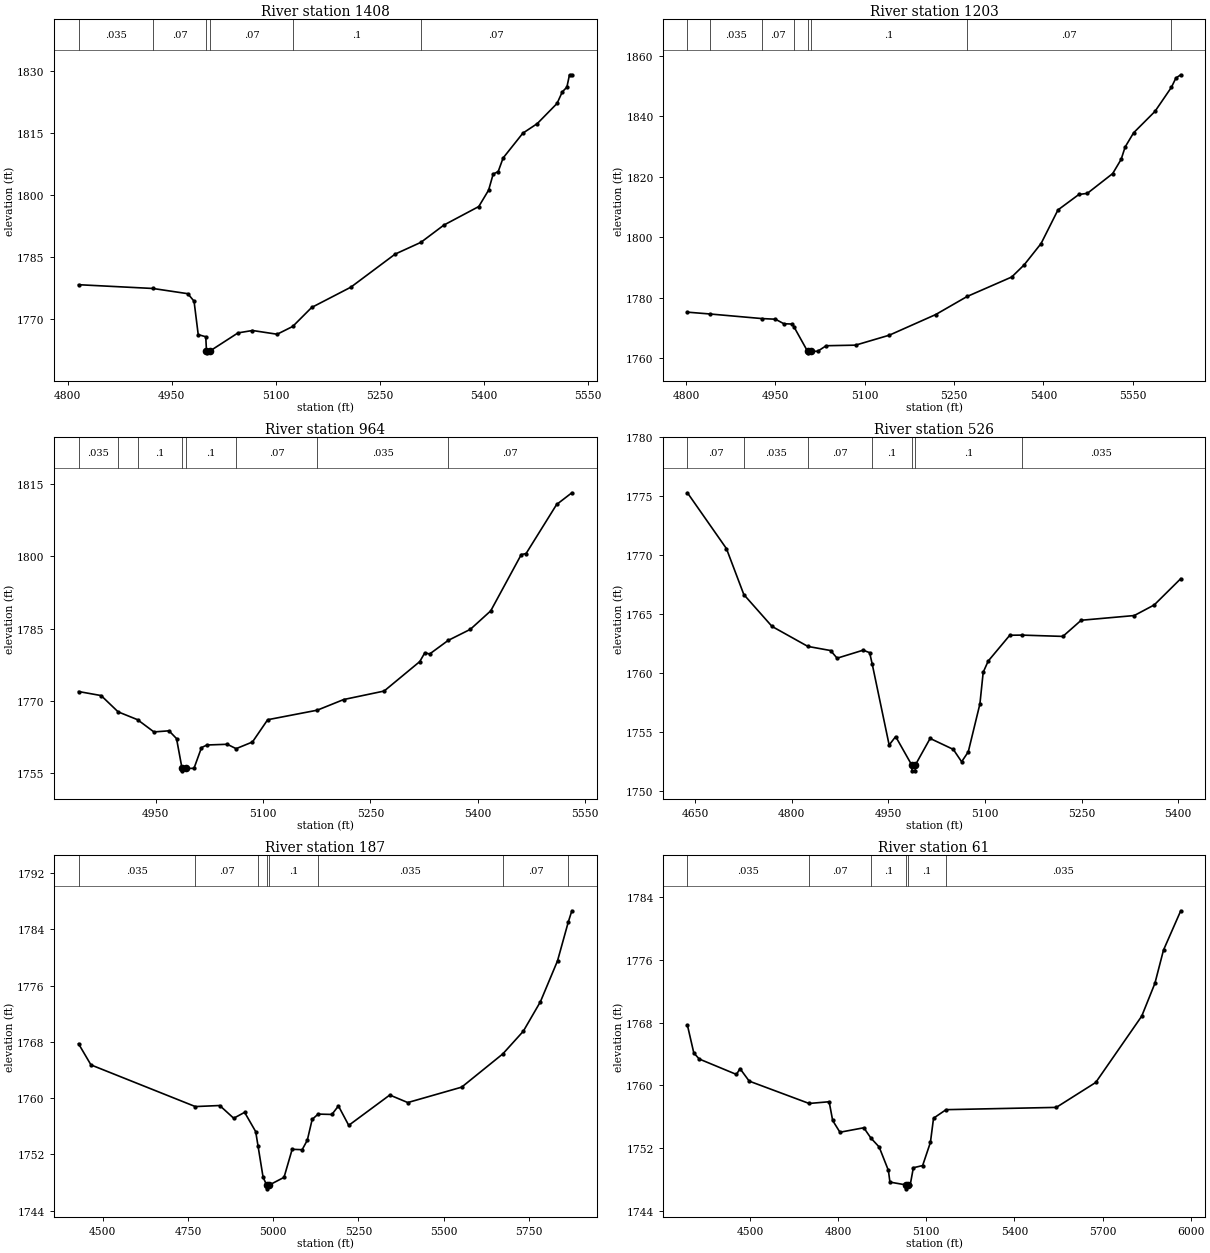
Type RM Length L Ch R = 1 ,1408    ,205,205,205
BEGIN DESCRIPTION:
Stream0444 3.0
END DESCRIPTION:
XS GIS Cut Line= 3
      1886324.98     13949874.99        1886175.       13949775.
      1885824.98     13949374.97
#Sta/Elev= 30
  4815.5 1778.36  4922.8 1777.45  4973.2 1776.19  4982.2 1774.38  4988.2 1766.32
  4999.1  1765.8  5000.1 1762.42  5000.5 1761.92  5005.7 1762.42  5045.6 1766.73
  5066.5 1767.31  5102.1 1766.41  5124.5 1768.28  5151.9 1772.87  5208.4 1777.76
  5272.4 1785.75  5309.5 1788.58  5342.7 1792.75    5393 1797.22  5407.2 1801.18
  5413.8 1805.07    5421 1805.65  5428.1 1808.93  5456.6 1814.92  5477.4 1817.23
  5505.9 1822.09  5513.5 1824.88  5520.1 1826.02  5523.9 1829.01  5527.3 1829.01
#Mann= 6 ,-1 , 0
  4815.5    .035       0  4922.8     .07       0  5000.1     .05       0
  5005.7     .07       0  5124.5      .1       0  5309.5     .07       0
Bank Sta=5000.1,5005.7
XS Rating Curve= 0 ,0
Exp/Cntr=0.3,0.1

Type RM Length L Ch R = 1 ,1203    ,239,239,239
BEGIN DESCRIPTION:
Mapping XS 159277bc
END DESCRIPTION:
XS GIS Cut Line= 2
      1886470.02     13949808.72      1885913.85     13949194.66
#Sta/Elev= 30
  4802.2 1775.23  4839.4 1774.64  4927.3 1773.11    4950  1772.9  4964.2  1771.4
  4978.4  1771.3  4981.2 1770.36    5004 1762.28  5004.5 1761.78  5009.6 1762.28
    5021  1762.3  5035.2 1764.13  5084.5 1764.32  5141.3 1767.62    5219 1774.42
  5271.9 1780.41  5346.8 1786.85  5367.7 1790.86  5396.1 1797.91  5424.5 1809.03
  5459.6 1814.14  5473.8 1814.51  5516.4 1821.06  5530.6 1825.76  5537.3 1829.84
  5551.5 1834.53  5587.4 1841.61    5615 1849.57  5622.5 1852.63  5630.7 1853.72
#Mann= 8 ,-1 , 0
  4802.2     .07       0  4839.4    .035       0  4927.3     .07       0
  4981.2      .1       0    5004     .05       0  5009.6      .1       0
  5271.9     .07       0    5615      .1       0
Bank Sta=5004,5009.6
XS Rating Curve= 0 ,0
Exp/Cntr=0.3,0.1

Type RM Length L Ch R = 1 ,964     ,438,438,438
BEGIN DESCRIPTION:
Stream0444 2.0
END DESCRIPTION:
XS GIS Cut Line= 3
        1886575.       13949675.        1886525.       13949525.
      1886125.01     13949175.01
#Sta/Elev= 30
  4841.9 1771.95  4873.5 1771.11  4897.3 1767.73  4924.4 1766.11  4947.3 1763.57
  4968.4  1763.8  4978.9 1762.19  4986.6    1756  4987.1  1755.5  4992.3    1756
  5003.3 1756.02  5013.8 1760.32  5021.4 1760.86  5049.8 1761.01  5062.2  1760.1
    5085 1761.48  5106.3  1766.1  5175.6 1768.08  5212.6 1770.29  5269.1 1772.05
  5318.9 1778.16    5326 1779.99  5332.7 1779.73  5358.6 1782.55  5389.6 1784.85
  5418.1 1788.68  5460.8 1800.36  5467.5 1800.56  5510.2 1810.74  5531.5 1813.17
#Mann= 8 ,-1 , 0
  4841.9    .035       0  4897.3      .1       0  4924.4      .1       0
  4986.6     .05       0  4992.3      .1       0  5062.2     .07       0
  5175.6    .035       0  5358.6     .07       0
Bank Sta=4986.6,4992.3
XS Rating Curve= 0 ,0
Exp/Cntr=0.3,0.1

Type RM Length L Ch R = 1 ,526     ,339,339,339
BEGIN DESCRIPTION:
Stream0444 1.0
END DESCRIPTION:
XS GIS Cut Line= 3
        1886925.     13949625.02        1886875.       13949275.
      1886474.99       13949175.
#Sta/Elev= 30
  4637.9 1775.29  4698.5 1770.55  4725.5 1766.65  4769.2 1763.95  4824.9 1762.25
  4860.2  1761.9  4870.3 1761.25  4910.7 1761.93  4920.8 1761.72  4924.7 1760.78
  4951.1 1753.88  4961.2  1754.6  4986.1 1752.19  4986.6 1751.69  4991.4 1751.69
  4991.8 1752.19  5014.7 1754.44  5050.7 1753.51  5063.6 1752.46  5073.9  1753.3
    5092 1757.37  5097.1 1760.06  5104.9 1761.01  5138.4  1763.2  5157.4 1763.21
  5220.8  1763.1  5249.2 1764.47  5331.6 1764.87  5362.6 1765.77  5403.8    1768
#Mann= 7 ,-1 , 0
  4637.9     .07       0  4725.5    .035       0  4824.9     .07       0
  4924.7      .1       0  4986.1     .05       0  4991.8      .1       0
  5157.4    .035       0
Bank Sta=4986.1,4991.8
XS Rating Curve= 0 ,0
Exp/Cntr=0.3,0.1

Type RM Length L Ch R = 1 ,187     ,126,126,126
BEGIN DESCRIPTION:
Stream0444 0.0
END DESCRIPTION:
XS GIS Cut Line= 4
      1887082.86     13949659.22      1887183.97     13949207.12
      1887091.46     13948982.97      1886353.08     13948916.84
#Sta/Elev= 30
  4428.8 1767.73  4465.3 1764.72  4771.4  1758.8    4843 1758.95    4884 1757.14
    4916 1757.98  4948.5 1755.24  4955.5 1753.16  4970.1 1748.78  4980.9 1747.61
  4981.3 1747.11  4986.6 1747.61  5031.6 1748.74  5055.5 1752.73  5084.8 1752.67
  5099.9 1754.02  5114.2 1756.98  5131.6 1757.73    5172 1757.68  5191.2 1758.89
  5221.4 1756.13  5341.8 1760.44  5394.6 1759.37  5552.7 1761.56  5673.5 1766.29
  5733.4  1769.5  5783.6 1773.69  5833.8  1779.5  5865.5 1785.04  5875.9 1786.62
#Mann= 8 ,-1 , 0
  4428.8    .035       0  4771.4     .07       0  4955.5      .1       0
  4980.9     .05       0  4986.6      .1       0  5131.6    .035       0
  5673.5     .07       0  5865.5    .035       0
Bank Sta=4980.9,4986.6
XS Rating Curve= 0 ,0
Exp/Cntr=0.3,0.1

Type RM Length L Ch R = 1 ,61      ,0,0,0
BEGIN DESCRIPTION:
Stream0444 0.1
END DESCRIPTION:
XS GIS Cut Line= 4
      1887113.86     13949693.18      1887287.48     13949180.99
      1887196.34     13948911.89      1886432.52     13948529.98
#Sta/Elev= 30
  4286.9 1767.68  4308.7 1764.13  4327.2 1763.36  4453.9 1761.39  4465.8 1762.14
  4497.2 1760.54  4701.1 1757.69  4769.3 1757.91  4781.2 1755.52    4806 1754.02
  4887.2 1754.59  4911.3 1753.28  4939.4 1752.14  4970.9 1749.15  4976.1 1747.66
  5030.9  1747.3  5031.3  1746.8  5036.6  1747.3  5045.2 1747.32  5055.8 1749.49
  5087.4 1749.77  5113.9 1752.73  5124.5 1755.81  5167.2  1756.9  5542.3 1757.19
  5676.5 1760.37    5833 1768.83  5877.8 1773.01  5907.1 1777.26  5965.8 1782.27
#Mann= 6 ,-1 , 0
  4286.9    .035       0  4701.1     .07       0  4911.3      .1       0
  5030.9     .05       0  5036.6      .1       0  5167.2    .035       0
Bank Sta=5030.9,5036.6
XS Rating Curve= 0 ,0
Exp/Cntr=0.3,0.1

Chan Stop Cuts=-1
Use User Specified Reach Order=0
Composite Channel Slope=5