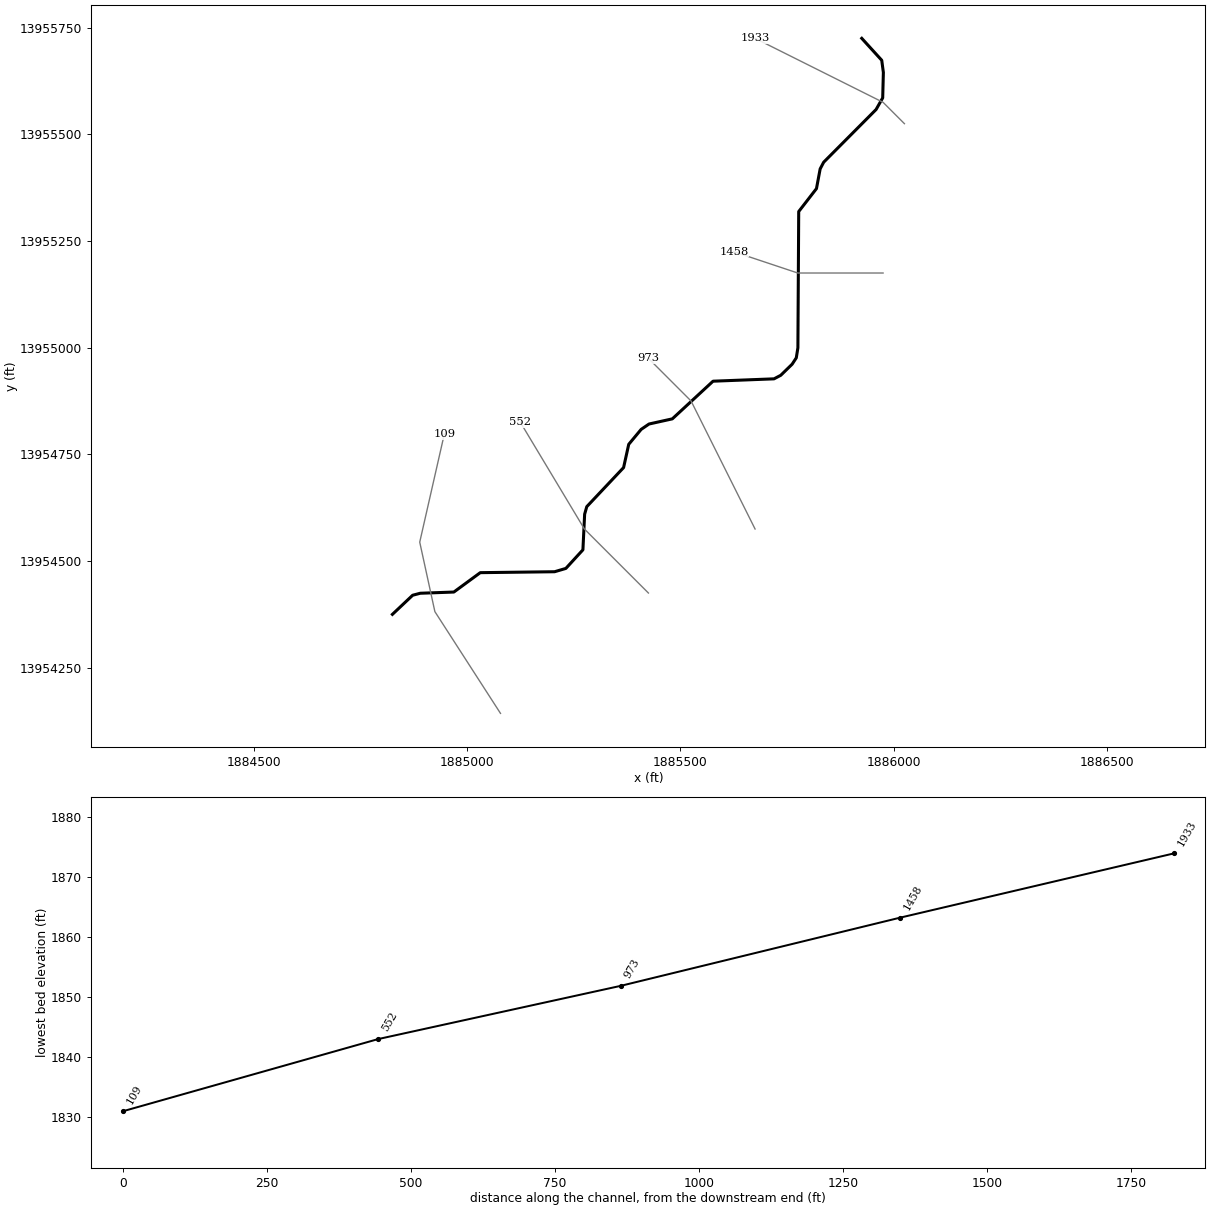
--- Stream0445.prj (project) ---

Proj Title=Stream0445 Base Level Engineering
Current Plan=p01
Default Exp/Contr=0.3,0.1
English Units
Geom File=g01
Flow File=f01
Plan File=p01
Y Axis Title=Elevation
X Axis Title(PF)=Main Channel Distance
X Axis Title(XS)=Station
BEGIN DESCRIPTION:
Stream0445
END DESCRIPTION:
DSS Export Rating Curves= 0
DSS Export Rating Curve Sorted= 0
DSS Export Volume Flow Curves= 0
DXF OffsetX= 0
DXF OffsetY= 0
DXF ScaleX= 1
DXF ScaleY= 10

--- Stream0445.p01 (plan) ---

Plan Title=Multiple Run
Short Identifier=Multiple
Geom File=g01
Flow File=f01
Subcritical Flow
K Sum by GR= 0
Std Step Tol= 0.01
Critical Tol= 0.01
Num of Std Step Trials= 20
Max Error Tol= 0.3
Flow Tol Ratio= 0.001
Split Flow NTrial= 30
Split Flow Tol= 0.02
Split Flow Ratio= 0.02
Log Output Level= 0
Friction Slope Method= 1
Unsteady Friction Slope Method= 2
Unsteady Bridges Friction Slope Method= 1
Parabolic Critical Depth
Global Vel Dist=  1 , 1 , 1
Global Log Level= 0
CheckData=True
Encroach Param= -1, 0, 0, 0
BEGIN DESCRIPTION:
Multiple Run
END DESCRIPTION:

--- Stream0445.f01 (steady flow) ---

Flow Title=Multiple
Program Version=4.10
Number of Profiles= 7
Profile Names=10-year,25-year,50-year,1pct_min,100-year,1pct_plu,500-year
River Rch & RM=Stream0445,Reach-1         ,1933
     588     971    1324     877    1749    3490    3006
Boundary for River Rch & Prof#=Stream0445,Reach-1         , 1
Up Type= 0
Dn Type= 3
Dn Slope=0.01
Boundary for River Rch & Prof#=Stream0445,Reach-1         , 2
Up Type= 0
Dn Type= 3
Dn Slope=0.01
Boundary for River Rch & Prof#=Stream0445,Reach-1         , 3
Up Type= 0
Dn Type= 3
Dn Slope=0.01
Boundary for River Rch & Prof#=Stream0445,Reach-1         , 4
Up Type= 0
Dn Type= 3
Dn Slope=0.01
Boundary for River Rch & Prof#=Stream0445,Reach-1         , 5
Up Type= 0
Dn Type= 3
Dn Slope=0.01
Boundary for River Rch & Prof#=Stream0445,Reach-1         , 6
Up Type= 0
Dn Type= 3
Dn Slope=0.01
Boundary for River Rch & Prof#=Stream0445,Reach-1         , 7
Up Type= 0
Dn Type= 3
Dn Slope=0.01
DSS Import GetInterval= 0
DSS Import GetPeak= 0
DSS Import FillOption= 0

--- Stream0445.g01 (geometry) ---

Geom Title=Existing Conditions
Program Version=4.10

River Reach=Stream0445      ,Reach-1
Reach XY= 30
        1885925.       13955725.      1885971.82     13955673.59
      1885975.65     13955645.03      1885974.08     13955585.46
       1885958.6     13955558.24      1885835.76     13955434.68
       1885827.5     13955418.97      1885818.86     13955372.83
      1885777.24     13955319.07      1885775.33     13954999.78
      1885771.57     13954976.22       1885761.8     13954961.26
      1885735.18     13954935.32      1885719.35     13954926.98
      1885576.47     13954921.45      1885481.02     13954833.19
      1885426.43     13954821.11      1885407.95      13954808.5
      1885378.89     13954773.57      1885366.81     13954718.98
      1885280.54     13954627.42      1885275.53     13954609.77
      1885271.49     13954526.25      1885231.52     13954482.68
      1885205.13     13954474.91      1885030.94     13954472.74
      1884969.04     13954427.32      1884890.22     13954424.47
      1884872.45     13954419.78        1884825.       13954375.

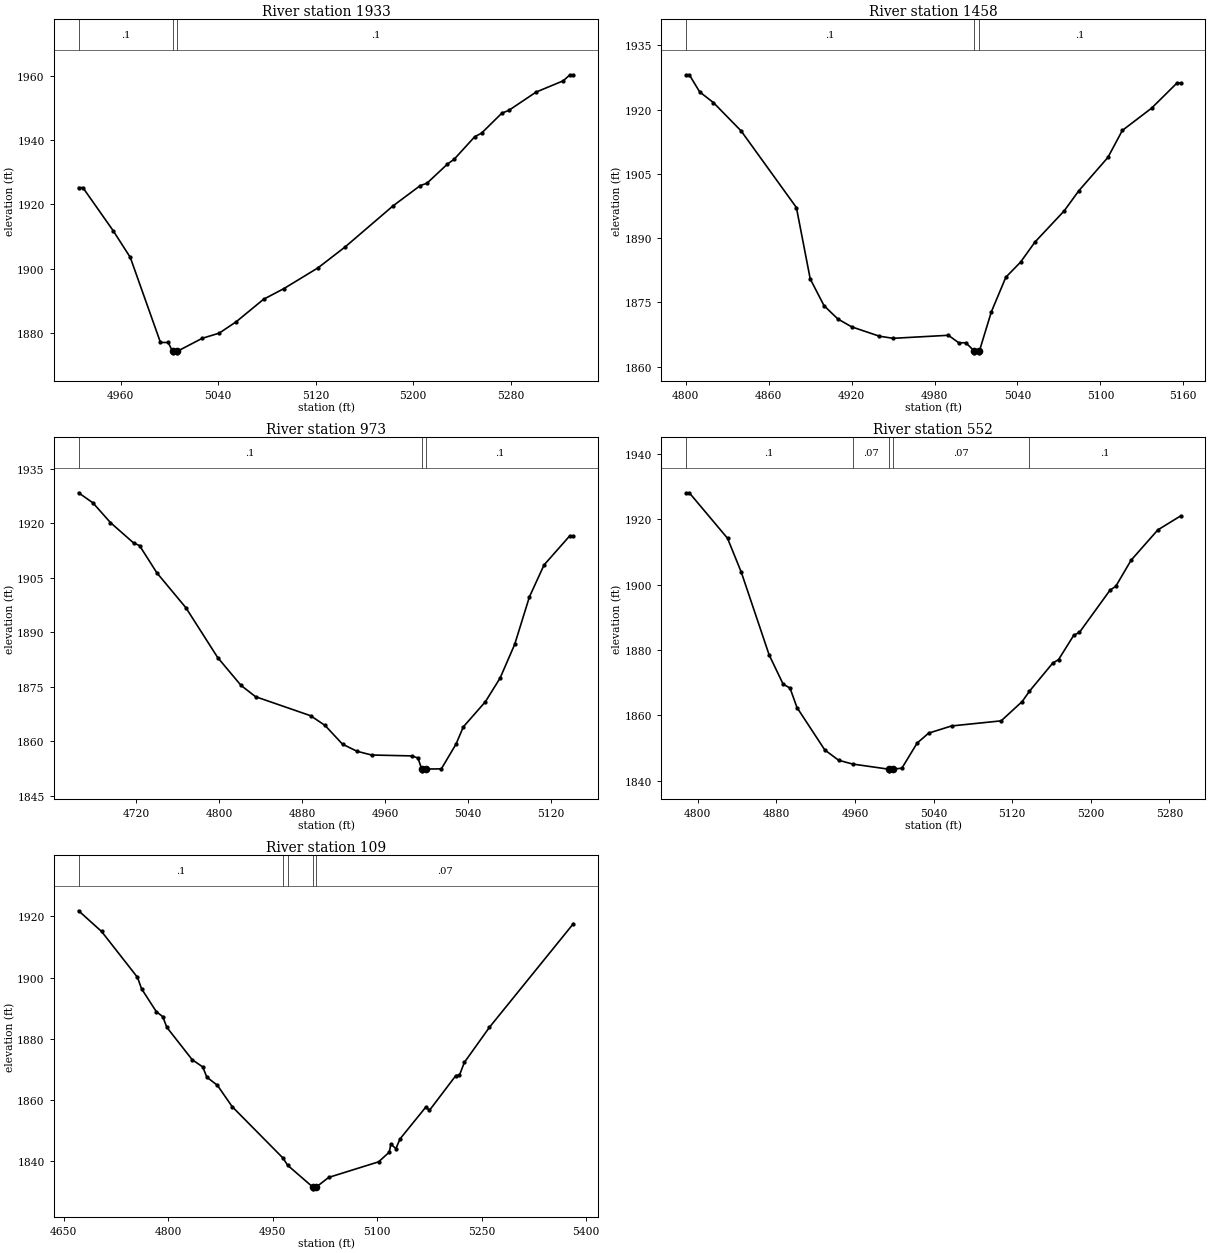
Type RM Length L Ch R = 1 ,1933    ,475,475,475
BEGIN DESCRIPTION:
Stream0445 4.0
END DESCRIPTION:
XS GIS Cut Line= 3
      1886025.01     13955524.99        1885975.       13955575.
      1885675.03     13955724.99
#Sta/Elev= 30
  4925.5 1925.24    4929 1925.24  4953.8 1911.89  4967.9 1903.57  4992.7 1877.12
    4999 1877.12  5002.6  1874.4  5002.9  1873.9  5006.4  1873.9  5006.6  1874.4
    5027 1878.42  5040.9 1880.02  5054.9 1883.57  5077.3 1890.54    5094 1893.86
    5122 1900.31  5144.4 1906.85  5183.5 1919.54  5205.9 1925.86  5211.4 1926.59
  5228.2 1932.54  5233.8 1934.07  5250.6 1941.05  5256.2 1942.15  5272.9 1948.38
  5278.5 1949.21  5300.9  1954.9  5323.2 1958.41  5328.8 1960.29  5331.6 1960.29
#Mann= 3 ,-1 , 0
  4925.5      .1       0  5002.6     .05       0  5006.6      .1       0
Bank Sta=5002.6,5006.6
XS Rating Curve= 0 ,0
Exp/Cntr=0.3,0.1

Type RM Length L Ch R = 1 ,1458    ,485,485,485
BEGIN DESCRIPTION:
Stream0445 3.0
END DESCRIPTION:
XS GIS Cut Line= 3
      1885974.99       13955175.        1885775.       13955175.
        1885625.       13955225.
#Sta/Elev= 30
    4800 1928.15  4802.5 1928.15    4810 1924.15    4820 1921.64    4840 1915.04
    4880 1897.15    4890 1880.49    4900 1874.23    4910 1871.13    4920 1869.29
    4940 1867.11    4950 1866.61    4990 1867.32  4997.5 1865.57  5002.6 1865.57
  5008.5 1863.72  5008.8 1863.22  5012.3 1863.22  5012.5 1863.72  5021.1 1872.81
  5031.6 1880.89  5042.2 1884.39  5052.7 1889.11  5073.8 1896.37  5084.3 1901.03
  5105.4 1908.84  5115.9 1915.16    5137 1920.34  5155.5 1926.25  5158.1 1926.25
#Mann= 3 ,-1 , 0
    4800      .1       0  5008.5     .05       0  5012.5      .1       0
Bank Sta=5008.5,5012.5
XS Rating Curve= 0 ,0
Exp/Cntr=0.3,0.1

Type RM Length L Ch R = 1 ,973     ,421,421,421
BEGIN DESCRIPTION:
Stream0445 2.0
END DESCRIPTION:
XS GIS Cut Line= 3
      1885674.98     13954575.04        1885525.       13954875.
      1885424.99     13954975.01
#Sta/Elev= 30
  4664.6 1928.45  4678.5 1925.65  4695.3 1920.24  4717.7 1914.61  4723.3 1913.92
    4740 1906.41    4768 1896.79  4798.7 1883.05  4821.1 1875.41  4835.1  1872.3
  4888.2 1867.05  4902.1 1864.38  4918.9 1859.22  4932.9 1857.27  4946.9 1856.24
    4986 1855.99  4991.6 1855.41  4995.2 1852.38  4995.4 1851.88  4999.2 1852.38
  5014.1 1852.42  5028.3 1859.24  5035.3 1863.98  5056.5 1870.88  5070.7  1877.4
  5084.8 1886.69    5099 1899.78  5113.1 1908.57  5137.9  1916.6  5141.4  1916.6
#Mann= 3 ,-1 , 0
  4664.6      .1       0  4995.2     .05       0  4999.2      .1       0
Bank Sta=4995.2,4999.2
XS Rating Curve= 0 ,0
Exp/Cntr=0.3,0.1

Type RM Length L Ch R = 1 ,552     ,443,443,443
BEGIN DESCRIPTION:
Stream0445 1.0
END DESCRIPTION:
XS GIS Cut Line= 3
      1885424.98     13954425.02        1885275.       13954575.
      1885125.02     13954824.96
#Sta/Elev= 30
  4787.9 1928.08  4791.4 1928.08  4830.3 1914.17  4844.4 1903.72  4872.7 1878.46
  4886.9 1869.55  4893.9 1868.35    4901  1862.4  4929.3 1849.42  4943.4 1846.27
  4957.6 1845.11  4994.5 1843.53  4994.7 1843.03  4998.5 1843.53  5007.8 1843.86
  5023.3 1851.53    5035 1854.56  5058.3 1856.76  5108.8 1858.32  5130.2 1864.23
  5137.6 1867.39  5161.3 1875.99  5167.2 1877.05  5182.7  1884.5  5188.5 1885.39
  5219.6 1898.29  5225.5 1899.49    5241 1907.44  5268.2 1916.71  5291.5 1921.01
#Mann= 5 ,-1 , 0
  4787.9      .1       0  4957.6     .07       0  4994.5     .05       0
  4998.5     .07       0  5137.6      .1       0
Bank Sta=4994.5,4998.5
XS Rating Curve= 0 ,0
Exp/Cntr=0.3,0.1

Type RM Length L Ch R = 1 ,109     ,0,0,0
BEGIN DESCRIPTION:
Stream0445 0.0
END DESCRIPTION:
XS GIS Cut Line= 4
      1885078.31     13954142.95      1884924.54     13954381.44
      1884889.05     13954544.26      1884946.72     13954797.67
#Sta/Elev= 30
  4671.6 1921.81  4704.6 1915.05  4756.1 1900.09    4762 1896.34  4783.1  1888.9
  4792.4 1887.24  4798.3 1883.75  4834.6 1873.21  4849.8 1870.83  4855.7 1867.49
  4870.9 1864.82    4892 1857.88  4964.9  1841.1  4971.8  1838.7  5008.2 1831.53
  5008.4 1831.03  5012.2 1831.53  5030.7 1834.77  5102.3 1839.85  5117.6 1843.02
  5119.8 1845.65  5127.1 1844.15    5133 1847.33  5170.1 1857.74  5175.3 1856.66
  5213.2 1868.03  5218.3 1868.11  5225.3 1872.29  5261.4 1883.78  5381.9 1917.62
#Mann= 5 ,-1 , 0
  4671.6      .1       0  4964.9     .07       0  4971.8     .07       0
  5008.2     .05       0  5012.2     .07       0
Bank Sta=5008.2,5012.2
XS Rating Curve= 0 ,0
Exp/Cntr=0.3,0.1

Chan Stop Cuts=-1
Use User Specified Reach Order=0
Composite Channel Slope=5