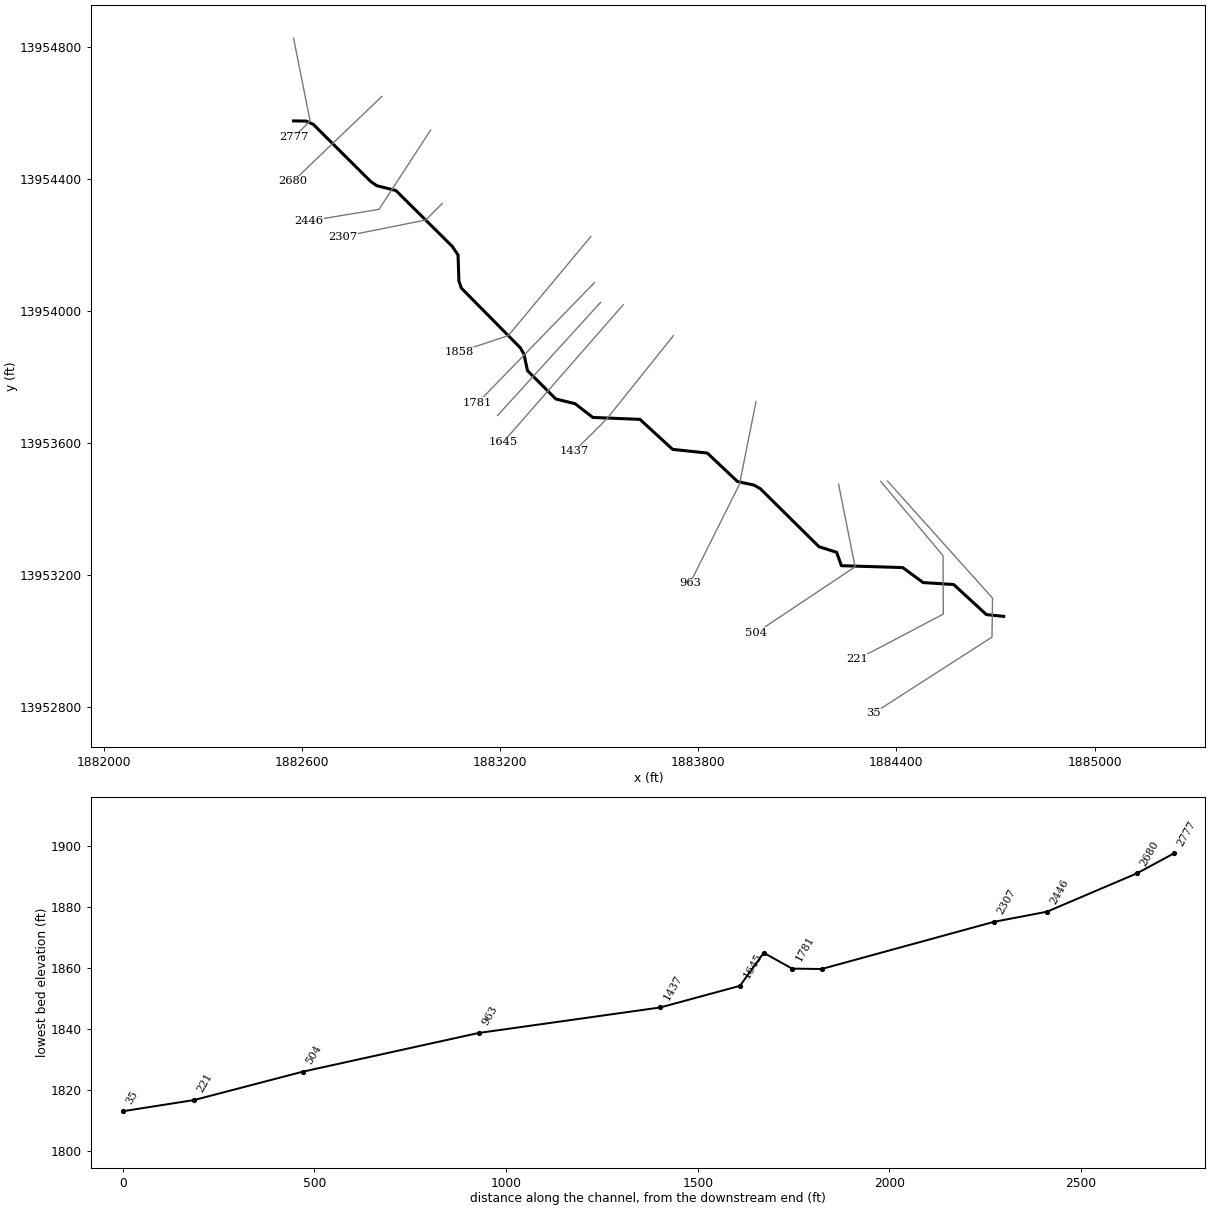
--- Stream0446.prj (project) ---

Proj Title=Stream0446 Base Level Engineering
Current Plan=p01
Default Exp/Contr=0.3,0.1
English Units
Geom File=g01
Flow File=f01
Plan File=p01
Y Axis Title=Elevation
X Axis Title(PF)=Main Channel Distance
X Axis Title(XS)=Station
BEGIN DESCRIPTION:
Stream0446
END DESCRIPTION:
DSS Export Rating Curves= 0
DSS Export Rating Curve Sorted= 0
DSS Export Volume Flow Curves= 0
DXF OffsetX= 0
DXF OffsetY= 0
DXF ScaleX= 1
DXF ScaleY= 10

--- Stream0446.p01 (plan) ---

Plan Title=Multiple Run
Short Identifier=Multiple
Geom File=g01
Flow File=f01
Subcritical Flow
K Sum by GR= 0
Std Step Tol= 0.01
Critical Tol= 0.01
Num of Std Step Trials= 20
Max Error Tol= 0.3
Flow Tol Ratio= 0.001
Split Flow NTrial= 30
Split Flow Tol= 0.02
Split Flow Ratio= 0.02
Log Output Level= 0
Friction Slope Method= 1
Unsteady Friction Slope Method= 2
Unsteady Bridges Friction Slope Method= 1
Parabolic Critical Depth
Global Vel Dist=  1 , 1 , 1
Global Log Level= 0
CheckData=True
Encroach Param= -1, 0, 0, 0
BEGIN DESCRIPTION:
Multiple Run
END DESCRIPTION:

--- Stream0446.f01 (steady flow) ---

Flow Title=Multiple
Program Version=4.10
Number of Profiles= 7
Profile Names=10-year,25-year,50-year,1pct_min,100-year,1pct_plu,500-year
River Rch & RM=Stream0446,Reach-1         ,2777
     509     832    1128     743    1482    2958    2520
Boundary for River Rch & Prof#=Stream0446,Reach-1         , 1
Up Type= 0
Dn Type= 3
Dn Slope=0.02
Boundary for River Rch & Prof#=Stream0446,Reach-1         , 2
Up Type= 0
Dn Type= 3
Dn Slope=0.02
Boundary for River Rch & Prof#=Stream0446,Reach-1         , 3
Up Type= 0
Dn Type= 3
Dn Slope=0.02
Boundary for River Rch & Prof#=Stream0446,Reach-1         , 4
Up Type= 0
Dn Type= 3
Dn Slope=0.02
Boundary for River Rch & Prof#=Stream0446,Reach-1         , 5
Up Type= 0
Dn Type= 3
Dn Slope=0.02
Boundary for River Rch & Prof#=Stream0446,Reach-1         , 6
Up Type= 0
Dn Type= 3
Dn Slope=0.02
Boundary for River Rch & Prof#=Stream0446,Reach-1         , 7
Up Type= 0
Dn Type= 3
Dn Slope=0.02
DSS Import GetInterval= 0
DSS Import GetPeak= 0
DSS Import FillOption= 0

--- Stream0446.g01 (geometry) ---

Geom Title=Existing Conditions
Program Version=4.10

River Reach=Stream0446      ,Reach-1
Reach XY= 30
        1882575.       13954575.      1882613.16     13954574.41
      1882634.79     13954564.48      1882808.33     13954391.65
      1882826.65     13954378.98      1882884.68     13954364.22
      1883055.37     13954195.15      1883072.85     13954169.11
      1883075.53     13954090.22      1883082.86     13954068.83
      1883261.37     13953888.21      1883272.46     13953868.95
      1883283.15     13953818.93      1883368.93     13953733.13
      1883427.17     13953718.86      1883480.93     13953677.25
      1883623.53     13953671.44      1883722.58     13953580.54
      1883827.42     13953569.46      1883918.96     13953483.18
      1883968.95     13953472.47      1883988.21     13953461.37
      1884165.57     13953285.85       1884219.2     13953268.94
      1884233.44      13953228.4      1884419.06     13953222.74
      1884480.98     13953177.36       1884573.5     13953171.39
      1884672.49     13953080.33        1884725.       13953075.

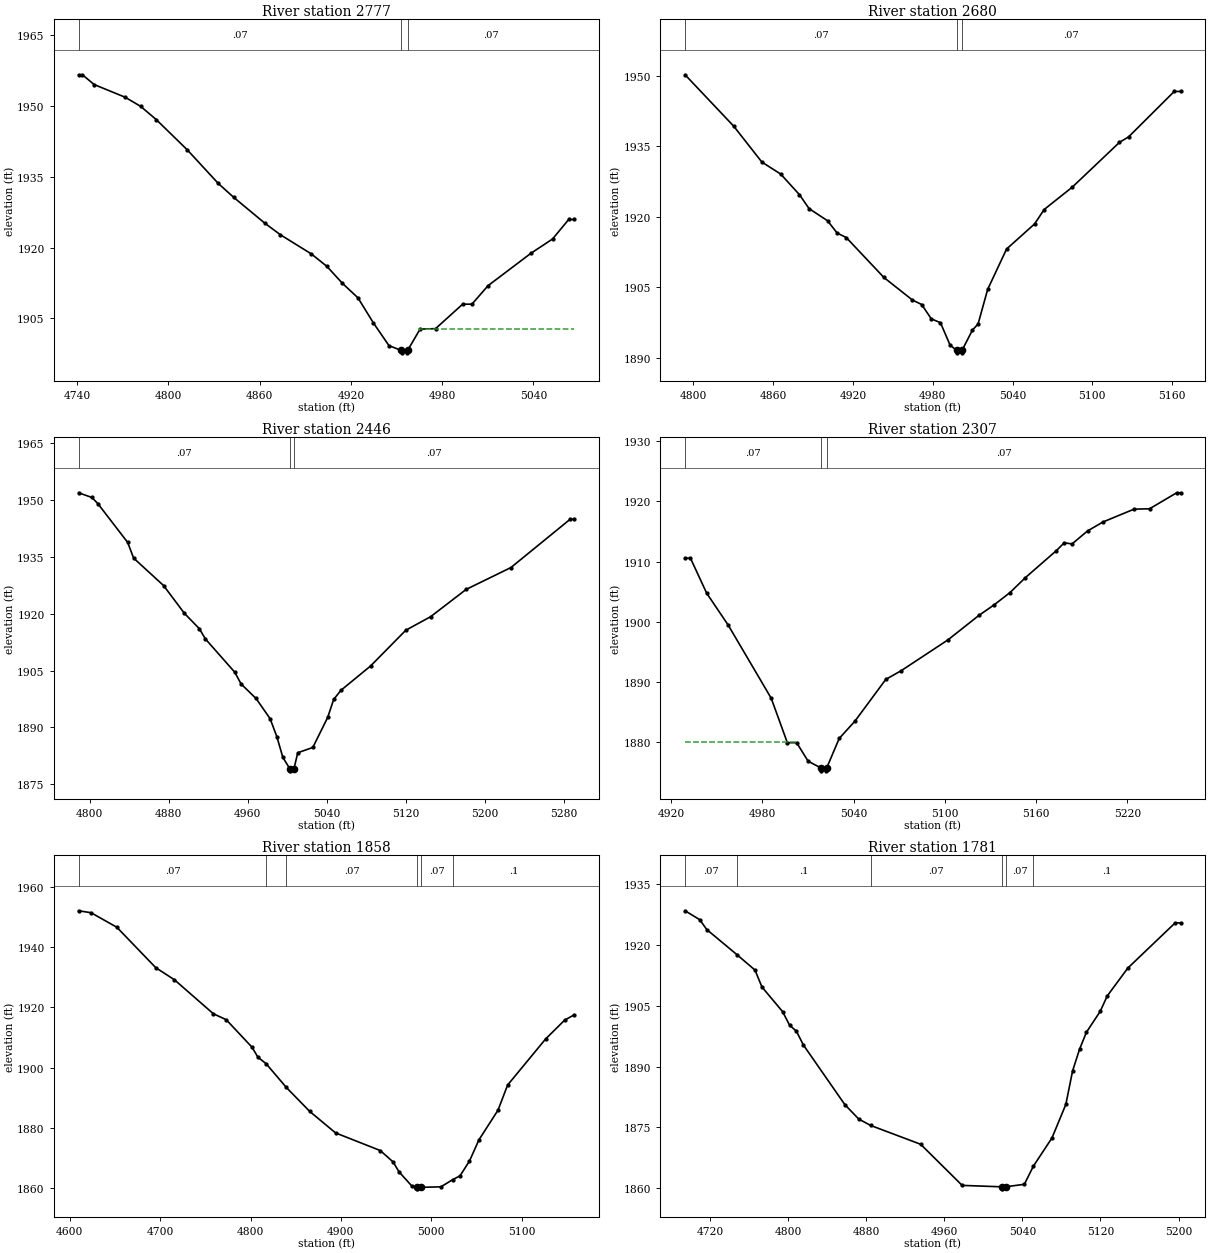
Type RM Length L Ch R = 1 ,2777    ,97,97,97
BEGIN DESCRIPTION:
Stream0446 6.0
END DESCRIPTION:
XS GIS Cut Line= 3
        1882575.       13954825.        1882625.       13954575.
      1882574.97     13954524.97
#Sta/Elev= 30
  4741.1 1956.62  4743.6 1956.62  4751.3 1954.55  4771.7 1951.86  4781.9 1949.92
  4792.1 1947.13  4812.5 1940.72  4832.9 1933.59  4843.1 1930.63  4863.5 1925.17
  4873.7 1922.73  4894.1 1918.66  4904.3 1916.02  4914.5 1912.43  4924.7 1909.36
  4934.9 1904.02  4945.1 1899.23  4953.3 1898.21  4953.5 1897.71    4957 1897.71
  4957.3 1898.21  4965.5 1902.73  4975.7 1902.84  4993.5 1908.02  4999.6 1908.02
  5010.2 1911.94  5038.5 1918.83  5052.6 1921.83  5063.2 1925.96  5066.8 1925.96
#Mann= 3 ,-1 , 0
  4741.1     .07       0  4953.3     .05       0  4957.3     .07       0
#XS Ineff= 2 , 0
                         4964.94         1902.85
Permanent Ineff=
       F       F
Bank Sta=4953.3,4957.3
XS Rating Curve= 0 ,0
Exp/Cntr=0.3,0.1

Type RM Length L Ch R = 1 ,2680    ,234,234,234
BEGIN DESCRIPTION:
Mapping XS 8aea120a
END DESCRIPTION:
XS GIS Cut Line= 2
      1882842.34     13954649.29      1882573.11     13954391.72
#Sta/Elev= 30
  4793.8 1950.17  4830.4 1939.24  4851.5 1931.64  4865.7 1929.08  4879.8  1924.7
    4887 1921.76  4900.9 1919.17  4908.1 1916.57    4915  1915.6  4943.3 1907.12
  4964.7 1902.34  4971.7 1901.38  4978.9 1898.34  4985.8 1897.52    4993 1892.79
    4998 1891.62  4998.2 1891.12  5001.7 1891.12    5002 1891.62  5009.8 1895.93
  5014.1 1897.26  5021.3 1904.59  5035.5 1913.16  5056.6  1918.5  5063.8 1921.56
  5084.9  1926.3  5120.4 1935.82  5127.3 1936.99  5161.6 1946.63  5166.4 1946.63
#Mann= 3 ,-1 , 0
  4793.8     .07       0    4998     .05       0    5002     .07       0
Bank Sta=4998,5002
XS Rating Curve= 0 ,0
Exp/Cntr=0.3,0.1

Type RM Length L Ch R = 1 ,2446    ,139,139,139
BEGIN DESCRIPTION:
Mapping XS be2ffab5
END DESCRIPTION:
XS GIS Cut Line= 3
      1882989.84     13954547.32      1882833.66     13954307.22
      1882621.85     13954272.34
#Sta/Elev= 30
  4788.9 1951.86  4802.3 1950.62  4808.3 1949.01  4838.5 1938.77  4844.5 1934.64
  4874.8  1927.4  4895.9 1920.06    4911 1916.02    4917 1913.35  4946.8 1904.55
  4953.2 1901.45  4968.3 1897.63  4982.5 1892.32  4989.4 1887.51  4995.4  1882.1
  5002.6 1879.05  5002.8 1878.55  5006.6 1879.05  5010.5 1883.32  5025.7 1884.71
  5040.8 1892.66  5046.8 1897.37  5054.1 1899.77  5084.1 1906.19  5119.7 1915.61
  5144.9  1919.2  5180.8 1926.39    5226 1932.14  5285.9 1944.87    5290 1944.87
#Mann= 3 ,-1 , 0
  4788.9     .07       0  5002.6     .05       0  5006.6     .07       0
Bank Sta=5002.6,5006.6
XS Rating Curve= 0 ,0
Exp/Cntr=0.3,0.1

Type RM Length L Ch R = 1 ,2307    ,449,449,449
BEGIN DESCRIPTION:
Stream0446 5.0
END DESCRIPTION:
XS GIS Cut Line= 3
      1883025.01     13954325.01        1882975.       13954275.
      1882724.97     13954224.99
#Sta/Elev= 30
  4929.3 1910.57  4932.8 1910.57  4943.5 1904.73  4957.6 1899.44  4985.9 1887.27
  4996.5 1879.88  5002.6 1879.88  5010.2  1876.8  5018.4  1875.7  5018.7  1875.2
  5022.2  1875.2  5022.4  1875.7  5030.6 1880.59  5040.8 1883.42  5061.2  1890.4
  5071.4 1891.86    5102 1896.96  5122.4 1901.04  5132.6 1902.83  5142.8 1904.83
    5153 1907.33  5173.4 1911.83  5178.5 1913.12  5183.6 1912.92  5193.8 1915.08
    5204 1916.58  5224.4 1918.71  5234.6 1918.77  5252.4 1921.43    5255 1921.43
#Mann= 3 ,-1 , 0
  4929.3     .07       0  5018.4     .05       0  5022.4     .07       0
#XS Ineff= 2 , 0
          5002.3 1880.06
Permanent Ineff=
       F       F
Bank Sta=5018.4,5022.4
XS Rating Curve= 0 ,0
Exp/Cntr=0.3,0.1

Type RM Length L Ch R = 1 ,1858    ,77,77,77
BEGIN DESCRIPTION:
Stream0446 4.0
END DESCRIPTION:
XS GIS Cut Line= 3
      1883475.01     13954225.01        1883225.       13953925.
      1883075.04     13953875.01
#Sta/Elev= 30
  4609.7 1952.04  4623.4  1951.4    4652 1946.57    4695 1933.17  4715.8 1929.12
  4758.8 1917.86  4773.1 1915.87  4801.7 1906.72  4808.2 1903.42  4817.4 1901.22
  4839.5 1893.42  4865.5 1885.43  4894.1 1878.29  4943.6 1872.43  4957.9 1868.63
  4964.4 1865.35  4978.8 1860.57  4984.6 1860.21  4984.8 1859.71  4988.6 1860.21
  5010.8 1860.38  5023.8 1862.76  5031.9 1864.02  5042.4 1868.95  5052.9    1876
    5074 1885.84  5084.6 1894.17  5126.7 1909.48  5147.8 1915.74  5158.3 1917.48
#Mann= 6 ,-1 , 0
  4609.7     .07       0  4817.4      .1       0  4839.5     .07       0
  4984.6     .05       0  4988.6     .07       0  5023.8      .1       0
Bank Sta=4984.6,4988.6
XS Rating Curve= 0 ,0
Exp/Cntr=0.3,0.1

Type RM Length L Ch R = 1 ,1781    ,74,74,74
BEGIN DESCRIPTION:
Mapping XS d305bfa6
END DESCRIPTION:
XS GIS Cut Line= 2
      1883485.86     13954085.46      1883132.24     13953721.31
#Sta/Elev= 30
  4694.5 1928.42  4709.5 1926.22  4716.7 1923.79  4747.5 1917.62  4766.1 1913.79
  4773.2 1909.63  4794.4 1903.54  4801.5 1900.21  4808.5 1898.72  4815.7 1895.31
  4858.1 1880.62  4872.3 1877.07  4884.5 1875.48  4935.8 1870.83  4978.3 1860.69
  5018.7 1860.34    5019 1859.84  5022.7 1860.34    5042 1860.96  5051.3 1865.45
  5070.3 1872.39  5084.5 1880.65  5091.4 1888.91  5098.6  1894.3  5105.6 1898.46
  5119.7  1903.6  5126.9 1907.41    5148 1914.29  5196.5 1925.44  5202.1 1925.44
#Mann= 6 ,-1 , 0
  4694.5     .07       0  4747.5      .1       0  4884.5     .07       0
  5018.7     .05       0  5022.7     .07       0  5051.3      .1       0
Bank Sta=5018.7,5022.7
XS Rating Curve= 0 ,0
Exp/Cntr=0.3,0.1

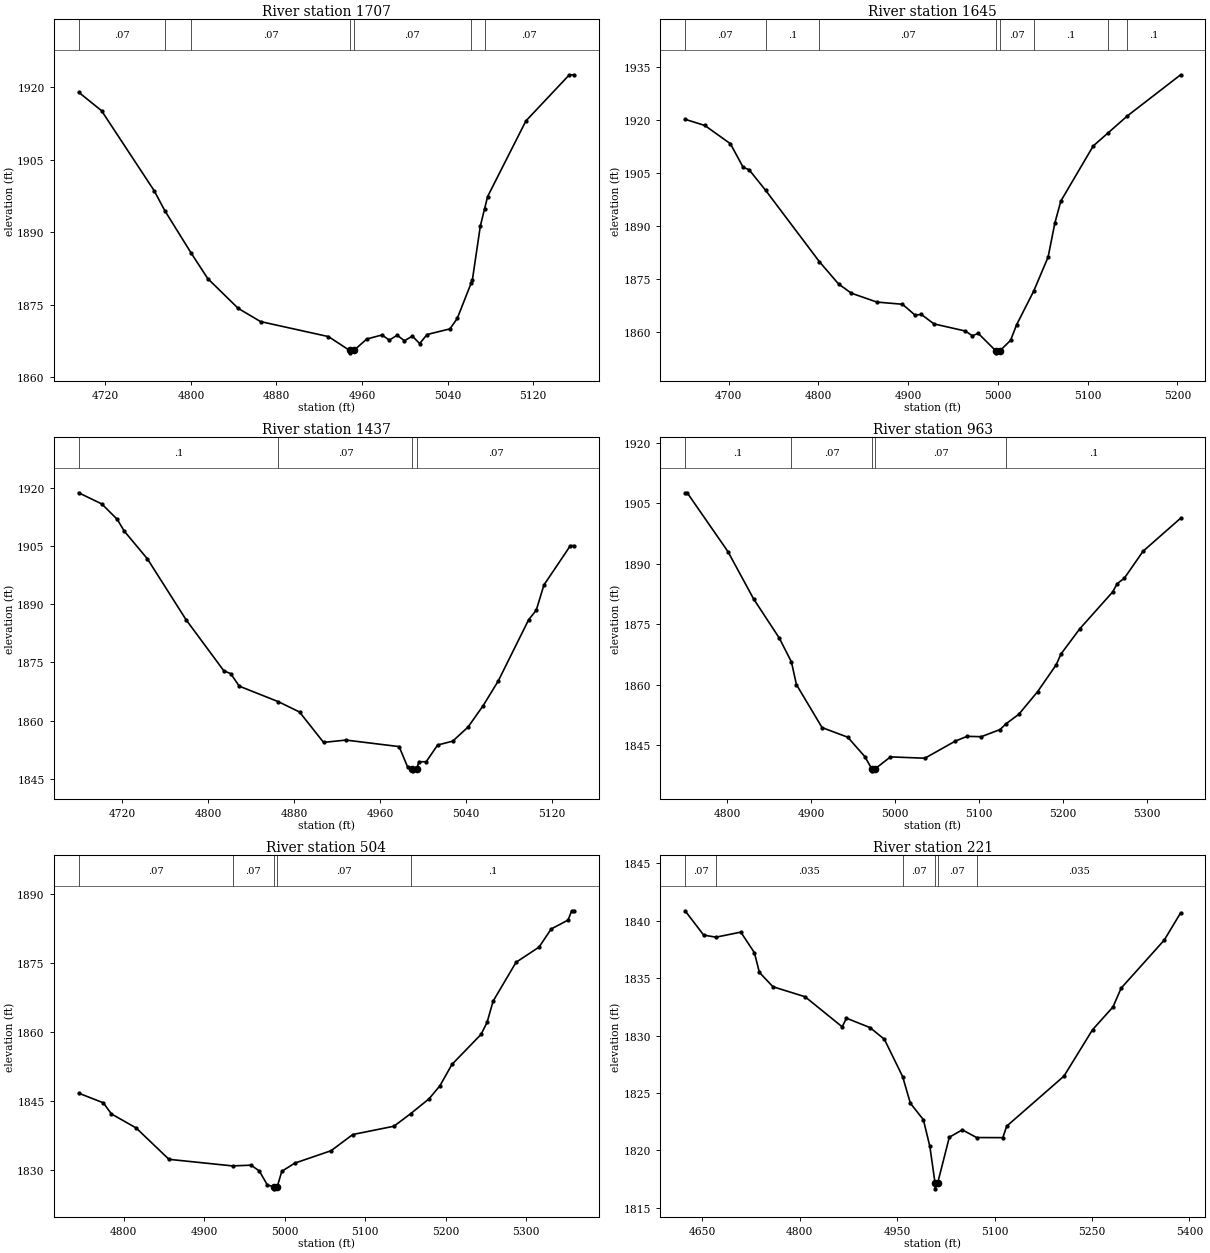
Type RM Length L Ch R = 1 ,1707    ,62,62,62
BEGIN DESCRIPTION:
Stream0446 4.1
END DESCRIPTION:
XS GIS Cut Line= 2
      1883504.49      13954025.7      1883192.66     13953683.31
#Sta/Elev= 30
  4695.1 1918.97  4716.5 1915.15  4765.8 1898.55  4775.6 1894.47  4800.4 1885.63
  4815.8 1880.39  4844.2 1874.24  4865.1  1871.5  4928.6 1868.39  4948.3 1865.53
  4948.5 1865.03  4952.3 1865.53  4964.4 1867.89  4978.6 1868.73  4985.4 1867.67
  4992.8 1868.67  4999.6 1867.53    5007  1868.5  5013.8 1866.95  5020.7 1868.82
  5042.1 1869.99  5048.9 1872.14  5061.8 1879.39  5063.1 1880.16  5070.5 1891.28
  5074.4 1894.77  5077.3 1897.37  5113.1 1913.03  5153.7 1922.58  5158.2 1922.58
#Mann= 7 ,-1 , 0
  4695.1     .07       0  4775.6      .1       0  4800.4     .07       0
  4948.3     .05       0  4952.3     .07       0  5061.8      .1       0
  5074.4     .07       0
Bank Sta=4948.3,4952.3
XS Rating Curve= 0 ,0
Exp/Cntr=0.3,0.1

Type RM Length L Ch R = 1 ,1645    ,208,208,208
BEGIN DESCRIPTION:
Mapping XS d0865764
END DESCRIPTION:
XS GIS Cut Line= 2
      1883572.93      13954018.3      1883209.55     13953602.51
#Sta/Elev= 30
  4651.4 1920.24  4673.4 1918.49  4701.9 1913.32  4716.1 1906.66  4722.7 1905.97
  4741.2 1900.13  4800.9 1880.01  4822.4 1873.66  4836.6 1871.06  4865.1 1868.54
  4893.6 1867.92  4907.8 1864.82  4914.5 1865.07  4928.7 1862.37  4963.8 1860.34
  4971.4 1859.02  4978.1 1859.68  4997.9 1854.68  4998.2 1854.18  5001.9 1854.68
  5014.1 1857.72  5020.8 1862.11  5039.9 1871.66  5055.9 1881.26  5063.5 1890.96
  5070.1 1897.11  5106.2  1912.7  5122.4 1916.31  5144.3 1921.21  5203.6 1932.83
#Mann= 8 ,-1 , 0
  4651.4     .07       0  4741.2      .1       0  4800.9     .07       0
  4997.9     .05       0  5001.9     .07       0  5039.9      .1       0
  5122.4     .07       0  5144.3      .1       0
Bank Sta=4997.9,5001.9
XS Rating Curve= 0 ,0
Exp/Cntr=0.3,0.1

Type RM Length L Ch R = 1 ,1437    ,474,474,474
BEGIN DESCRIPTION:
Stream0446 3.0
END DESCRIPTION:
XS GIS Cut Line= 3
      1883724.98     13953924.98        1883525.       13953675.
      1883425.03     13953575.03
#Sta/Elev= 30
  4679.4 1918.65    4701 1915.77  4715.4  1911.8  4721.8 1908.81  4743.4 1901.66
  4779.4 1885.99  4814.6 1872.83    4821 1872.09    4829 1868.87  4865.5 1864.86
  4885.1 1862.22  4907.5 1854.39  4928.3 1854.99  4977.9 1853.31  4985.9 1847.99
  4990.3 1847.57  4990.6 1847.07  4994.3 1847.57  4996.3 1849.41  5003.1 1849.41
  5013.7 1853.71  5027.8 1854.72    5042 1858.32  5056.1 1863.84  5070.2 1870.21
  5098.5 1885.97  5105.6 1888.42  5112.7 1894.89  5137.4 1905.05  5140.9 1905.05
#Mann= 4 ,-1 , 0
  4679.4      .1       0  4865.5     .07       0  4990.3     .05       0
  4994.3     .07       0
Bank Sta=4990.3,4994.3
XS Rating Curve= 0 ,0
Exp/Cntr=0.3,0.1

Type RM Length L Ch R = 1 ,963     ,459,459,459
BEGIN DESCRIPTION:
Stream0446 2.0
END DESCRIPTION:
XS GIS Cut Line= 3
        1883975.       13953725.        1883925.       13953475.
      1883774.98     13953174.96
#Sta/Elev= 30
  4749.5 1907.62    4752 1907.62  4800.5 1893.05  4831.1 1881.32  4861.7  1871.6
  4876.2 1865.68  4882.1 1860.08  4912.7  1849.4  4943.3 1847.02  4963.7 1842.19
  4971.9 1839.18  4972.1 1838.68  4975.9 1839.18  4994.2 1842.14  5035.2 1841.81
  5071.5 1846.06  5085.5 1847.24  5102.3 1847.14  5124.6  1848.9  5132.2  1850.4
    5147 1852.68  5169.4 1858.29  5191.7 1864.99  5197.3 1867.64  5219.7 1873.89
  5258.8 1883.01  5264.4 1885.11  5272.8 1886.43  5295.1 1893.12  5339.9 1901.32
#Mann= 5 ,-1 , 0
  4749.5      .1       0  4876.2     .07       0  4971.9     .05       0
  4975.9     .07       0  5132.2      .1       0
Bank Sta=4971.9,4975.9
XS Rating Curve= 0 ,0
Exp/Cntr=0.3,0.1

Type RM Length L Ch R = 1 ,504     ,283,283,283
BEGIN DESCRIPTION:
Stream0446 1.0
END DESCRIPTION:
XS GIS Cut Line= 3
      1884224.99     13953475.04        1884275.       13953225.
      1883974.96     13953024.97
#Sta/Elev= 30
  4744.1 1846.73  4774.7 1844.64  4784.9 1842.21  4815.5 1839.18  4856.3 1832.36
  4935.3 1830.93  4958.3 1831.09  4968.5 1829.84  4978.7 1826.74  4986.9 1826.45
  4987.1 1825.95  4990.9 1826.45  4996.5 1829.76  5012.6 1831.53  5057.7 1834.23
  5084.7 1837.75  5135.8 1839.55  5156.4 1842.25  5179.4  1845.5  5192.9 1848.33
  5207.9 1852.98    5244 1859.49  5251.5 1862.11    5259 1866.72  5287.5 1875.15
  5316.1 1878.46  5331.1 1882.38  5352.1 1884.32  5356.6 1886.34  5359.7 1886.34
#Mann= 5 ,-1 , 0
  4744.1     .07       0  4935.3     .07       0  4986.9     .05       0
  4990.9     .07       0  5156.4      .1       0
Bank Sta=4986.9,4990.9
XS Rating Curve= 0 ,0
Exp/Cntr=0.3,0.1

Type RM Length L Ch R = 1 ,221     ,186,186,186
BEGIN DESCRIPTION:
Stream0446 0.0
END DESCRIPTION:
XS GIS Cut Line= 4
      1884352.78      13953483.3       1884541.2     13953258.79
      1884542.09     13953081.92       1884282.7     13952945.38
#Sta/Elev= 30
  4623.3 1840.87  4651.9 1838.75  4670.9 1838.57  4709.1 1839.01    4730 1837.22
  4737.7  1835.5  4758.6 1834.25    4808 1833.38  4865.2 1830.76  4871.8 1831.51
  4908.1 1830.69  4930.2 1829.67  4958.3 1826.42  4970.2  1824.1  4990.2 1822.67
  5000.2 1820.34  5008.2 1817.14  5008.4 1816.64  5012.2 1817.14  5030.2 1821.14
  5050.2 1821.78  5072.2 1821.11  5112.6  1821.1  5118.5  1822.1  5206.7 1826.46
  5250.8 1830.51  5282.1 1832.48  5294.8 1834.13  5361.2 1838.32  5386.4 1840.69
#Mann= 6 ,-1 , 0
  4623.3     .07       0  4670.9    .035       0  4958.3     .07       0
  5008.2     .05       0  5012.2     .07       0  5072.2    .035       0
Bank Sta=5008.2,5012.2
XS Rating Curve= 0 ,0
Exp/Cntr=0.3,0.1

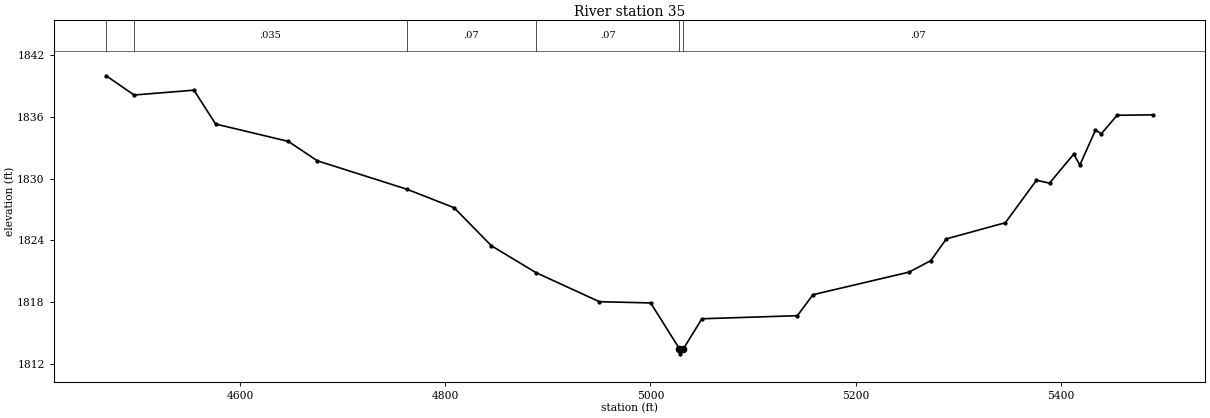
Type RM Length L Ch R = 1 ,35      ,0,0,0
BEGIN DESCRIPTION:
Stream0446 0.1
END DESCRIPTION:
XS GIS Cut Line= 4
      1884373.42     13953484.41      1884691.13     13953130.24
      1884689.39     13953012.19      1884330.03     13952781.29
#Sta/Elev= 30
  4469.2    1840  4496.4 1838.13  4554.8  1838.6  4575.9 1835.31  4646.8 1833.62
  4675.2 1831.73  4762.4 1828.97  4808.5 1827.17  4844.9 1823.47  4888.3 1820.86
  4950.2 1818.03  5000.2 1817.91  5028.2 1813.46  5028.5 1812.96  5032.2 1813.46
  5050.2 1816.37  5143.3 1816.67  5158.5 1818.71  5252.3 1820.91  5273.4 1822.02
  5288.6 1824.14  5346.1 1825.71  5376.5 1829.84  5389.2 1829.56  5412.8 1832.38
  5418.8 1831.32  5433.9 1834.69  5439.9 1834.38  5455.1 1836.16  5490.2  1836.2
#Mann= 6 ,-1 , 0
  4469.2     .07       0  4496.4    .035       0  4762.4     .07       0
  4888.3     .07       0  5028.2     .05       0  5032.2     .07       0
Bank Sta=5028.2,5032.2
XS Rating Curve= 0 ,0
Exp/Cntr=0.3,0.1

Chan Stop Cuts=-1
Use User Specified Reach Order=0
Composite Channel Slope=5