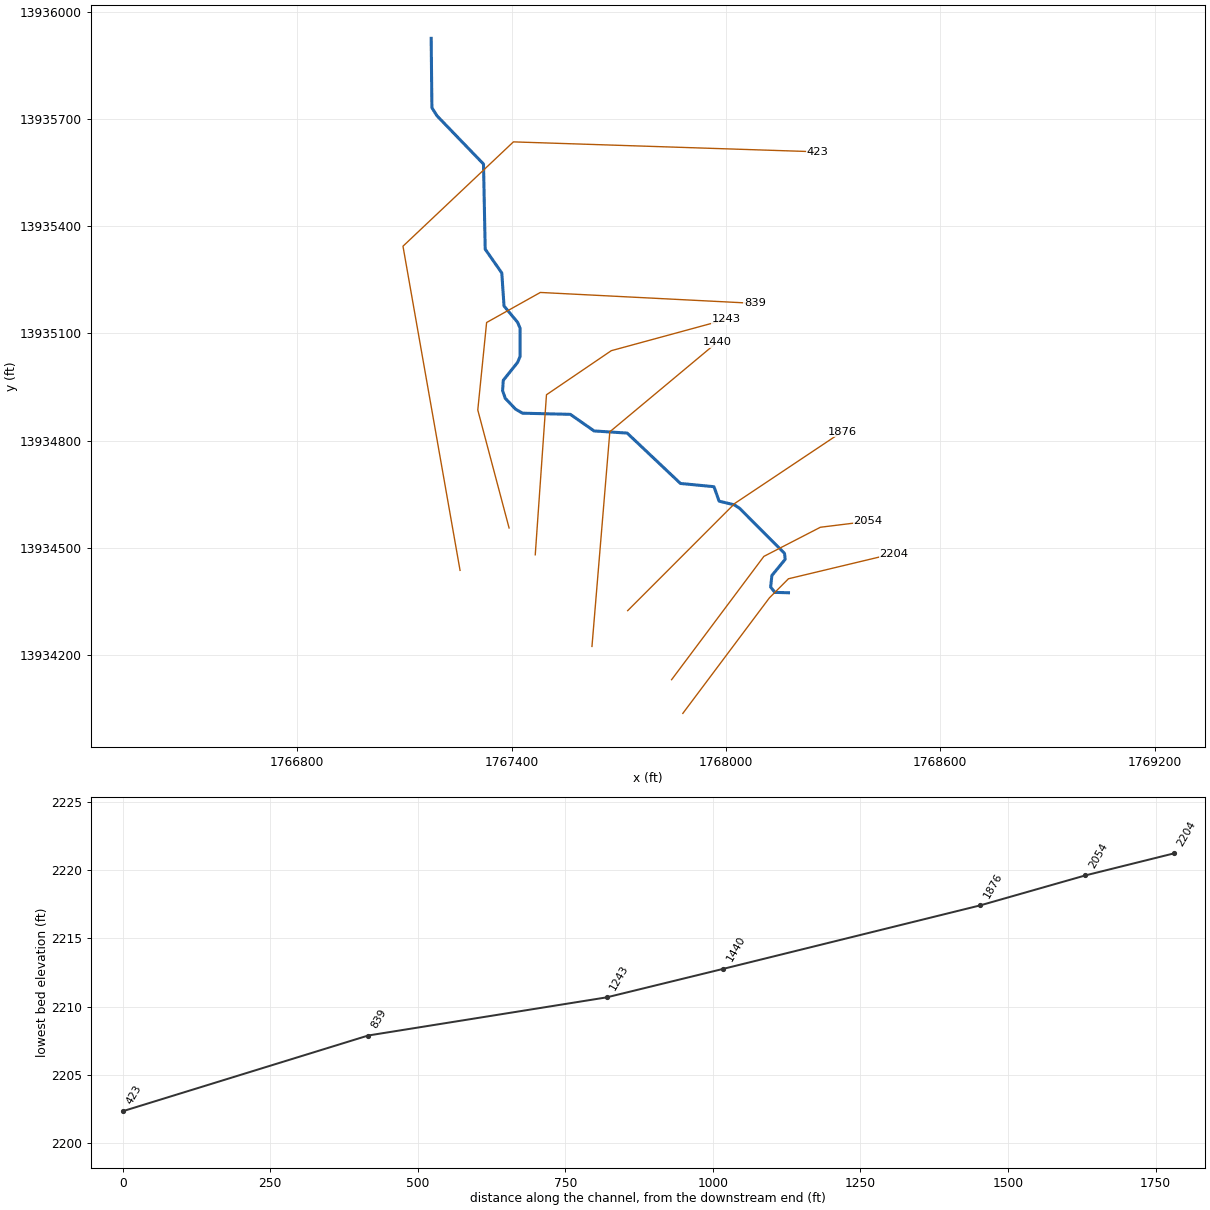
--- Stream1000.prj (project) ---

Proj Title=Stream1000 Base Level Engineering
Current Plan=p01
Default Exp/Contr=0.3,0.1
English Units
Geom File=g01
Flow File=f01
Plan File=p01
BEGIN DESCRIPTION:
Stream1000
END DESCRIPTION:

--- Stream1000.p01 (plan) ---

Plan Title=Multiple Run
Short Identifier=Multiple
Geom File=g01
Flow File=f01
Subcritical Flow
K Sum by GR= 0
Std Step Tol= 0.01
Critical Tol= 0.01
Num of Std Step Trials= 20
Max Error Tol= 0.3
Flow Tol Ratio= 0.001
Split Flow NTrial= 30
Split Flow Tol= 0.02
Split Flow Ratio= 0.02
Log Output Level= 0
Friction Slope Method= 1
Unsteady Friction Slope Method= 2
Unsteady Bridges Friction Slope Method= 1
Parabolic Critical Depth
Global Vel Dist=  1 , 1 , 1
Global Log Level= 0
CheckData=True
Encroach Param= -1, 0, 0, 0
BEGIN DESCRIPTION:
Multiple Run
END DESCRIPTION:

--- Stream1000.f01 (steady flow) ---

Flow Title=Multiple
Number of Profiles=7
Profile Names=10-year,25-year,50-year,1pct_min,100-year,1pct_plu,500-year
River Rch & RM= Stream1000,Reach-1,2204
     617    1020    1391     918    1833    3657    3142
Boundary for River Rch & Prof#=Stream1000,Reach-1,1
Up Type=0
Dn Type=3
Dn Slope=0.005
Boundary for River Rch & Prof#=Stream1000,Reach-1,2
Up Type=0
Dn Type=3
Dn Slope=0.005
Boundary for River Rch & Prof#=Stream1000,Reach-1,3
Up Type=0
Dn Type=3
Dn Slope=0.005
Boundary for River Rch & Prof#=Stream1000,Reach-1,4
Up Type=0
Dn Type=3
Dn Slope=0.005
Boundary for River Rch & Prof#=Stream1000,Reach-1,5
Up Type=0
Dn Type=3
Dn Slope=0.005
Boundary for River Rch & Prof#=Stream1000,Reach-1,6
Up Type=0
Dn Type=3
Dn Slope=0.005
Boundary for River Rch & Prof#=Stream1000,Reach-1,7
Up Type=0
Dn Type=3
Dn Slope=0.005

--- Stream1000.g01 (geometry) ---

Geom Title=Existing Conditions

River Reach=Stream1000,Reach-1
Reach XY= 30
      1768175.00     13934375.00      1768136.97     13934376.05
      1768124.99     13934390.94      1768128.55     13934423.19
      1768165.74     13934468.42      1768163.91     13934485.04
      1768038.00     13934611.31      1768023.03     13934620.95
      1767980.80     13934631.05      1767966.52     13934671.50
      1767872.63     13934680.54      1767723.50     13934821.39
      1767630.98     13934827.36      1767564.49     13934873.77
      1767430.63     13934876.99      1767411.19     13934888.23
      1767382.34     13934918.61      1767374.89     13934940.19
      1767376.77     13934968.83      1767416.86     13935018.94
      1767423.88     13935035.54      1767423.90     13935114.45
      1767416.91     13935131.04      1767378.86     13935176.60
      1767372.64     13935269.02      1767326.22     13935335.50
      1767321.46     13935573.54      1767191.43     13935708.24
      1767177.05     13935730.85      1767175.00     13935925.00

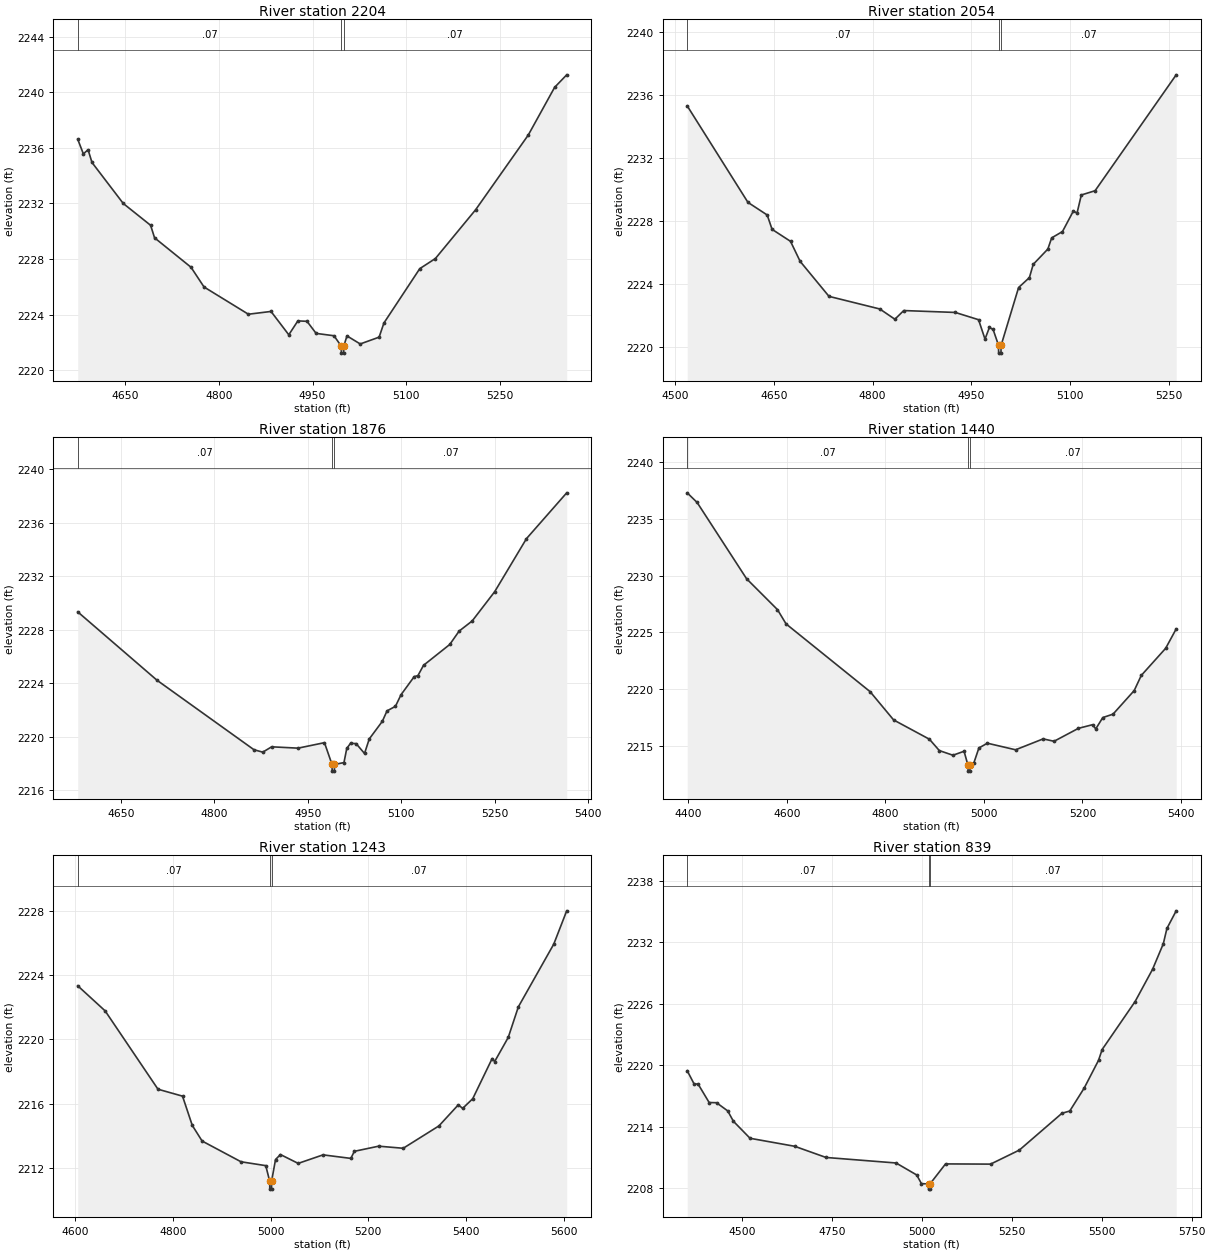
Type RM Length L Ch R = 1,2204,150,150,150
BEGIN DESCRIPTION:
Stream1000 4.0
END DESCRIPTION:
XS GIS Cut Line= 4
      1767879.34     13934037.77      1768121.55     13934360.71
      1768174.93     13934414.09      1768469.18     13934484.40
#Sta/Elev= 30
  4574.6 2236.61  4583.6 2235.56  4591.1 2235.86  4597.4 2234.94  4647.4 2231.99
  4691.1 2230.42  4697.4 2229.52  4755.7 2227.40  4776.5 2225.98  4847.4 2224.02
  4883.6 2224.22  4912.0 2222.54  4926.5 2223.54  4941.1 2223.51  4955.7 2222.64
  4984.3 2222.47  4995.9 2221.72  4996.1 2221.22  4999.6 2221.22  4999.9 2221.72
  5005.0 2222.46  5026.2 2221.88  5056.4 2222.37  5064.1 2223.39  5121.4 2227.30
  5146.4 2228.03  5210.7 2231.54  5294.9 2236.92  5337.0 2240.35  5356.3 2241.25
#Mann=3,-1,0
  4574.6    0.07       0  4995.9    0.05       0  4999.9    0.07       0
Bank Sta=4995.9,4999.9
Exp/Cntr=0.3,0.1

Type RM Length L Ch R = 1,2054,178,178,178
BEGIN DESCRIPTION:
Stream1000 3.0
END DESCRIPTION:
XS GIS Cut Line= 4
      1767847.88     13934131.95      1768106.12     13934476.66
      1768264.34     13934558.14      1768396.85     13934574.46
#Sta/Elev= 30
  4518.7 2235.29  4610.9 2229.17  4640.1 2228.37  4647.5 2227.46  4675.5 2226.70
  4690.1 2225.43  4733.9 2223.21  4811.0 2222.41  4833.9 2221.76  4847.4 2222.31
  4925.6 2222.19  4960.9 2221.73  4970.7 2220.50  4977.4 2221.24  4983.0 2221.11
  4991.2 2220.11  4991.4 2219.61  4994.9 2219.61  4995.2 2220.11  5021.7 2223.77
  5038.1 2224.40  5043.9 2225.24  5066.1 2226.21  5071.9 2226.92  5088.3 2227.32
  5104.8 2228.62  5110.4 2228.49  5116.9 2229.64  5137.8 2229.91  5260.9 2237.26
#Mann=3,-1,0
  4518.7    0.07       0  4991.2    0.05       0  4995.2    0.07       0
Bank Sta=4991.2,4995.2
Exp/Cntr=0.3,0.1

Type RM Length L Ch R = 1,1876,436,436,436
BEGIN DESCRIPTION:
Stream1000 2.0
END DESCRIPTION:
XS GIS Cut Line= 3
      1767724.98     13934324.98      1768025.00     13934625.00
      1768324.96     13934824.97
#Sta/Elev= 30
  4580.7 2229.34  4708.0 2224.22  4863.6 2219.02  4877.7 2218.84  4891.9 2219.24
  4934.3 2219.14  4976.7 2219.55  4988.8 2217.92  4989.1 2217.42  4992.6 2217.42
  4992.8 2217.92  5008.0 2218.06  5012.5 2219.12  5018.5 2219.50  5027.5 2219.48
  5041.0 2218.74  5048.6 2219.83  5069.6 2221.15  5077.1 2221.93  5090.6 2222.27
  5099.6 2223.14  5120.7 2224.49  5126.7 2224.57  5135.7 2225.34  5177.8 2226.90
  5192.8 2227.90  5213.8 2228.66  5249.9 2230.85  5300.9 2234.82  5365.5 2238.25
#Mann=3,-1,0
  4580.7    0.07       0  4988.8    0.05       0  4992.8    0.07       0
Bank Sta=4988.8,4992.8
Exp/Cntr=0.3,0.1

Type RM Length L Ch R = 1,1440,197,197,197
BEGIN DESCRIPTION:
Stream1000 1.0
END DESCRIPTION:
XS GIS Cut Line= 3
      1767625.00     13934224.94      1767675.00     13934825.00
      1767974.96     13935074.97
#Sta/Elev= 30
  4397.8 2237.29  4417.9 2236.44  4518.3 2229.72  4581.0 2227.00  4598.5 2225.74
  4769.1 2219.77  4816.8 2217.28  4889.5 2215.58  4909.6 2214.58  4937.2 2214.17
  4959.8 2214.52  4967.8 2213.27  4968.1 2212.77  4971.6 2212.77  4971.8 2213.27
  4979.8 2213.51  4989.9 2214.81  5007.1 2215.23  5064.4 2214.65  5120.3 2215.61
  5142.5 2215.40  5191.9 2216.54  5220.6 2216.86  5227.1 2216.49  5241.4 2217.49
  5262.2 2217.79  5305.2 2219.87  5319.5 2221.20  5369.0 2223.59  5390.4 2225.30
#Mann=3,-1,0
  4397.8    0.07       0  4967.8    0.05       0  4971.8    0.07       0
Bank Sta=4967.8,4971.8
Exp/Cntr=0.3,0.1

Type RM Length L Ch R = 1,1243,404,404,404
BEGIN DESCRIPTION:
Stream1000 0.1
END DESCRIPTION:
XS GIS Cut Line= 4
      1767466.28     13934481.07      1767497.68     13934928.55
      1767679.08     13935051.77      1768000.53     13935139.17
#Sta/Elev= 30
  4605.2 2223.33  4661.3 2221.77  4769.5 2216.90  4819.7 2216.47  4839.7 2214.65
  4859.8 2213.68  4939.5 2212.39  4990.1 2212.15  4998.1 2211.19  4998.4 2210.69
  5001.9 2210.69  5002.1 2211.19  5010.1 2212.53  5020.2 2212.84  5056.5 2212.29
  5107.4 2212.82  5164.3 2212.60  5171.4 2213.04  5221.2 2213.36  5271.5 2213.23
  5344.6 2214.62  5384.3 2215.93  5393.2 2215.71  5413.8 2216.31  5453.6 2218.81
  5458.7 2218.62  5486.5 2220.12  5507.2 2222.02  5579.7 2225.92  5606.2 2227.99
#Mann=3,-1,0
  4605.2    0.07       0  4998.1    0.05       0  5002.1    0.07       0
Bank Sta=4998.1,5002.1
Exp/Cntr=0.3,0.1

Type RM Length L Ch R = 1,839,416,416,416
BEGIN DESCRIPTION:
Stream1000 0.0
END DESCRIPTION:
XS GIS Cut Line= 5
      1767393.04     13934556.09      1767305.44     13934885.91
      1767330.14     13935130.52      1767480.54     13935214.56
      1768080.76     13935184.02
#Sta/Elev= 30
  4346.6 2219.45  4366.2 2218.13  4376.5 2218.17  4407.6 2216.35  4428.2 2216.33
  4459.3 2215.53  4475.1 2214.52  4521.4 2212.86  4645.5 2212.08  4732.7 2210.99
  4927.7 2210.45  4985.1 2209.28  4998.2 2208.44  5017.9 2208.40  5018.2 2207.90
  5021.7 2207.90  5021.9 2208.40  5065.3 2210.36  5190.6 2210.34  5270.7 2211.71
  5389.2 2215.30  5410.9 2215.52  5450.9 2217.75  5491.0 2220.47  5501.0 2221.52
  5592.7 2226.20  5641.2 2229.34  5671.2 2231.84  5681.2 2233.33  5707.0 2235.05
#Mann=3,-1,0
  4346.6    0.07       0  5017.9    0.05       0  5021.9    0.07       0
Bank Sta=5017.9,5021.9
Exp/Cntr=0.3,0.1

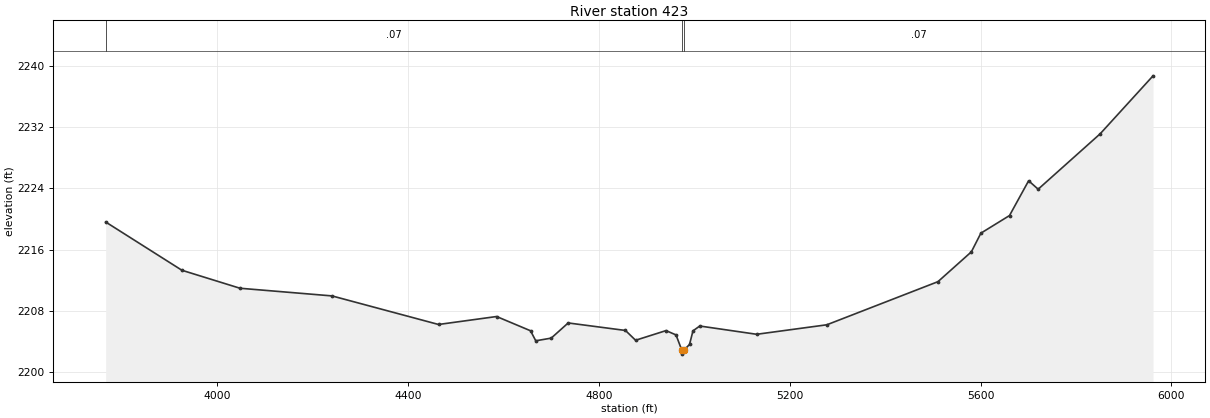
Type RM Length L Ch R = 1,423,0,0,0
BEGIN DESCRIPTION:
Stream1000 0.2
END DESCRIPTION:
XS GIS Cut Line= 4
      1767255.82     13934437.60      1767096.09     13935343.86
      1767405.12     13935635.52      1768255.81     13935607.75
#Sta/Elev= 30
  3765.5 2219.61  3925.3 2213.31  4047.2 2210.96  4240.1 2209.96  4463.5 2206.23
  4585.3 2207.27  4656.4 2205.41  4667.4 2204.10  4699.8 2204.45  4735.4 2206.43
  4855.5 2205.45  4876.7 2204.17  4940.5 2205.43  4961.5 2204.87  4973.7 2202.86
  4973.9 2202.36  4977.7 2202.86  4989.8 2203.62  4997.1 2205.40  5011.3 2206.03
  5130.6 2204.95  5277.8 2206.19  5510.8 2211.82  5580.8 2215.71  5600.8 2218.15
  5660.8 2220.45  5700.9 2224.99  5720.9 2223.89  5850.9 2231.12  5961.8 2238.69
#Mann=3,-1,0
  3765.5    0.07       0  4973.7    0.05       0  4977.7    0.07       0
Bank Sta=4973.7,4977.7
Exp/Cntr=0.3,0.1

Chan Stop Cuts=-1