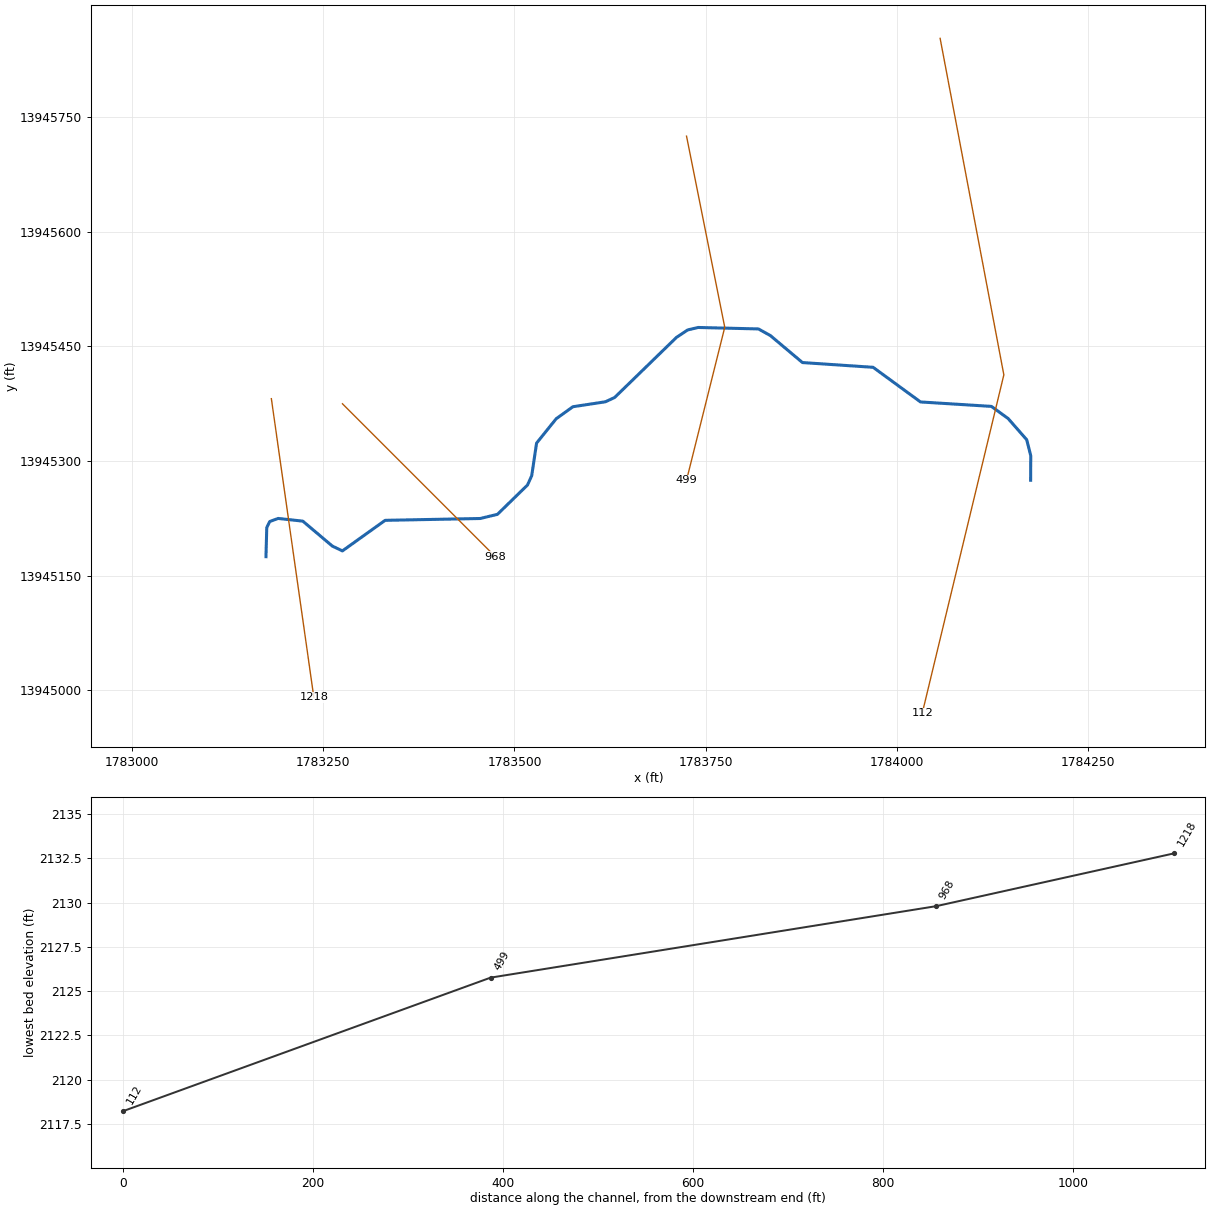
--- Stream1002.prj (project) ---

Proj Title=Stream1002 Base Level Engineering
Current Plan=p01
Default Exp/Contr=0.3,0.1
English Units
Geom File=g01
Flow File=f01
Plan File=p01
BEGIN DESCRIPTION:
Stream1002
END DESCRIPTION:

--- Stream1002.p01 (plan) ---

Plan Title=Multiple Run
Short Identifier=Multiple
Geom File=g01
Flow File=f01
Subcritical Flow
K Sum by GR= 0
Std Step Tol= 0.01
Critical Tol= 0.01
Num of Std Step Trials= 20
Max Error Tol= 0.3
Flow Tol Ratio= 0.001
Split Flow NTrial= 30
Split Flow Tol= 0.02
Split Flow Ratio= 0.02
Log Output Level= 0
Friction Slope Method= 1
Unsteady Friction Slope Method= 2
Unsteady Bridges Friction Slope Method= 1
Parabolic Critical Depth
Global Vel Dist=  1 , 1 , 1
Global Log Level= 0
CheckData=True
Encroach Param= -1, 0, 0, 0
BEGIN DESCRIPTION:
Multiple Run
END DESCRIPTION:

--- Stream1002.f01 (steady flow) ---

Flow Title=Multiple
Number of Profiles=7
Profile Names=10-year,25-year,50-year,1pct_min,100-year,1pct_plu,500-year
River Rch & RM= Stream1002,Reach-1,1218
     680    1131    1548    1026    2047    4085    3537
Boundary for River Rch & Prof#=Stream1002,Reach-1,1
Up Type=0
Dn Type=3
Dn Slope=0.005
Boundary for River Rch & Prof#=Stream1002,Reach-1,2
Up Type=0
Dn Type=3
Dn Slope=0.005
Boundary for River Rch & Prof#=Stream1002,Reach-1,3
Up Type=0
Dn Type=3
Dn Slope=0.005
Boundary for River Rch & Prof#=Stream1002,Reach-1,4
Up Type=0
Dn Type=3
Dn Slope=0.005
Boundary for River Rch & Prof#=Stream1002,Reach-1,5
Up Type=0
Dn Type=3
Dn Slope=0.005
Boundary for River Rch & Prof#=Stream1002,Reach-1,6
Up Type=0
Dn Type=3
Dn Slope=0.005
Boundary for River Rch & Prof#=Stream1002,Reach-1,7
Up Type=0
Dn Type=3
Dn Slope=0.005

--- Stream1002.g01 (geometry) ---

Geom Title=Existing Conditions

River Reach=Stream1002,Reach-1
Reach XY= 30
      1783175.00     13945175.00      1783176.05     13945213.03
      1783179.92     13945220.98      1783190.94     13945225.01
      1783223.19     13945221.47      1783261.71     13945188.93
      1783274.96     13945182.55      1783330.86     13945222.53
      1783455.11     13945224.93      1783477.70     13945230.36
      1783516.97     13945268.64      1783522.54     13945280.88
      1783528.90     13945323.54      1783554.53     13945355.36
      1783576.43     13945371.11      1783618.91     13945377.56
      1783631.02     13945383.19      1783711.71     13945461.64
      1783726.50     13945471.53      1783740.22     13945474.75
      1783819.02     13945472.84      1783834.63     13945464.19
      1783876.60     13945428.86      1783969.03     13945422.65
      1784030.98     13945377.35      1784123.70     13945371.54
      1784145.55     13945355.69      1784169.87     13945327.94
      1784175.15     13945307.07      1784175.00     13945275.00

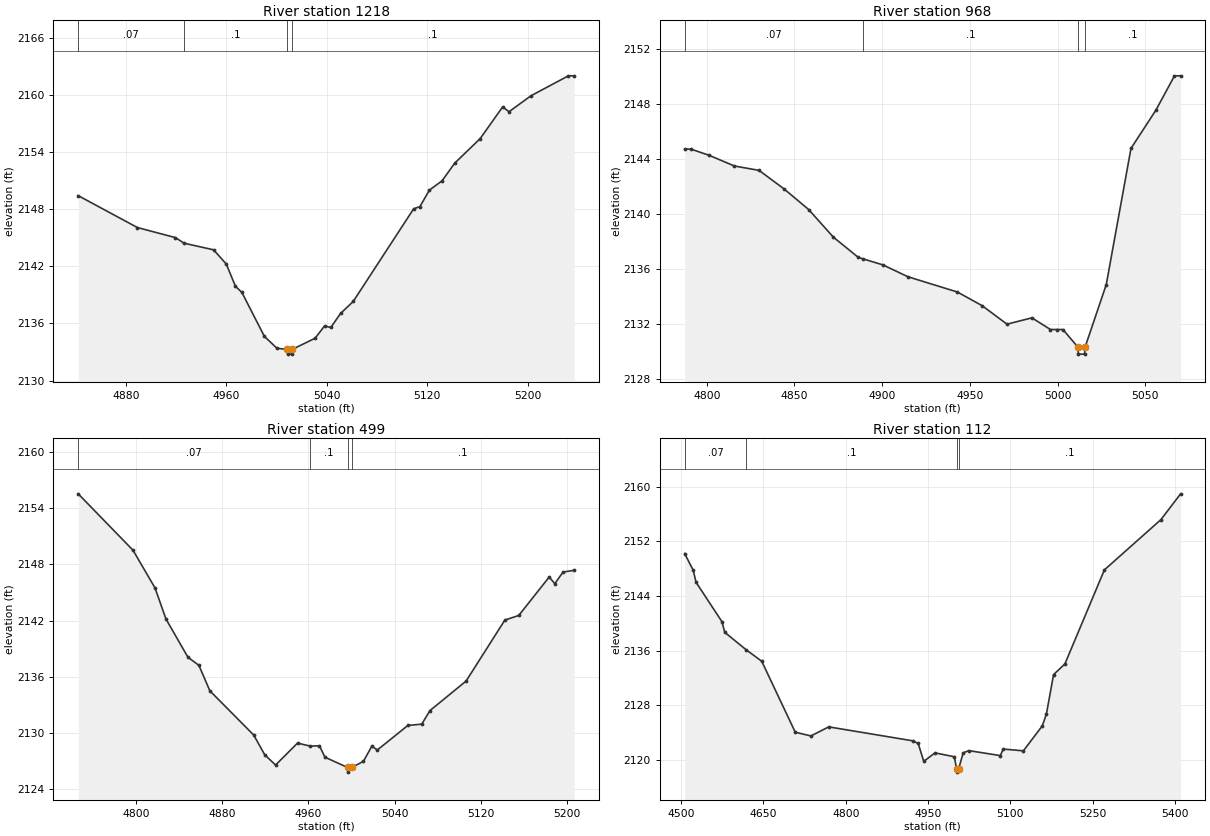
Type RM Length L Ch R = 1,1218,250,250,250
BEGIN DESCRIPTION:
Stream1002 3.0
END DESCRIPTION:
XS GIS Cut Line= 2
      1783182.06     13945381.64      1783237.62     13944990.97
#Sta/Elev= 30
  4842.2 2149.43  4889.3 2146.08  4919.6 2145.02  4926.5 2144.43  4949.9 2143.74
  4960.0 2142.25  4967.3 2139.91  4972.4 2139.27  4990.3 2134.65  5000.4 2133.39
  5008.5 2133.28  5008.8 2132.78  5012.3 2132.78  5012.5 2133.28  5030.7 2134.45
  5038.2 2135.74  5043.2 2135.58  5050.9 2137.05  5061.0 2138.31  5109.1 2148.05
  5114.1 2148.28  5121.6 2150.01  5131.7 2150.99  5141.8 2152.85  5162.0 2155.42
  5179.9 2158.75  5185.0 2158.25  5202.4 2159.92  5232.2 2162.02  5236.8 2162.02
#Mann=4,-1,0
  4842.2    0.07       0  4926.5     0.1       0  5008.5    0.05       0
  5012.5     0.1       0
Bank Sta=5008.5,5012.5
Exp/Cntr=0.3,0.1

Type RM Length L Ch R = 1,968,469,469,469
BEGIN DESCRIPTION:
Stream1002 2.0
END DESCRIPTION:
XS GIS Cut Line= 3
      1783275.01     13945374.99      1783425.00     13945225.00
      1783474.98     13945175.02
#Sta/Elev= 28
  4787.4 2144.72  4790.9 2144.72  4801.5 2144.26  4815.7 2143.49  4829.8 2143.17
  4844.0 2141.83  4858.1 2140.32  4872.2 2138.31  4886.4 2136.84  4888.9 2136.74
  4900.5 2136.29  4914.7 2135.43  4942.9 2134.32  4957.1 2133.32  4971.2 2131.98
  4985.4 2132.44  4996.0 2131.59  4999.5 2131.59  5003.1 2131.59  5011.7 2130.30
  5011.9 2129.80  5015.4 2129.80  5015.7 2130.30  5027.8 2134.86  5041.9 2144.77
  5056.1 2147.55  5066.7 2150.05  5070.2 2150.05
#Mann=4,-1,0
  4787.4    0.07       0  4888.9     0.1       0  5011.7    0.05       0
  5015.7     0.1       0
Bank Sta=5011.7,5015.7
Exp/Cntr=0.3,0.1

Type RM Length L Ch R = 1,499,387,387,387
BEGIN DESCRIPTION:
Stream1002 1.0
END DESCRIPTION:
XS GIS Cut Line= 3
      1783725.00     13945724.98      1783775.00     13945475.00
      1783725.00     13945274.99
#Sta/Elev= 30
  4745.9 2155.57  4796.9 2149.52  4817.3 2145.49  4827.5 2142.16  4847.9 2138.07
  4858.1 2137.20  4868.3 2134.47  4909.1 2129.73  4919.3 2127.62  4929.4 2126.52
  4949.8 2128.87  4961.5 2128.55  4970.2 2128.58  4975.3 2127.36  4996.3 2126.26
  4996.5 2125.76  5000.3 2126.26  5011.1 2126.92  5018.9 2128.54  5024.0 2128.13
  5052.4 2130.76  5065.3 2130.90  5073.0 2132.36  5106.5 2135.51  5142.6 2142.05
  5155.5 2142.54  5183.8 2146.66  5189.0 2145.95  5196.7 2147.19  5207.0 2147.38
#Mann=4,-1,0
  4745.9    0.07       0  4961.5     0.1       0  4996.3    0.05       0
  5000.3     0.1       0
Bank Sta=4996.3,5000.3
Exp/Cntr=0.3,0.1

Type RM Length L Ch R = 1,112,0,0,0
BEGIN DESCRIPTION:
Stream1002 0.0
END DESCRIPTION:
XS GIS Cut Line= 3
      1784056.64     13945852.87      1784139.97     13945412.79
      1784033.20     13944970.08
#Sta/Elev= 30
  4506.7 2150.23  4522.3 2147.77  4527.4 2146.02  4574.6 2140.25  4579.7 2138.69
  4618.9 2136.12  4647.0 2134.46  4708.1 2124.06  4736.6 2123.51  4769.1 2124.84
  4921.8 2122.80  4932.0 2122.41  4942.2 2119.79  4962.6 2121.03  4997.9 2120.46
  5001.8 2118.71  5002.0 2118.21  5005.8 2118.71  5014.0 2121.04  5024.3 2121.36
  5081.7 2120.63  5086.8 2121.59  5123.6 2121.33  5158.1 2124.99  5165.5 2126.70
  5178.6 2132.50  5199.2 2134.06  5271.2 2147.84  5374.1 2155.20  5410.0 2158.98
#Mann=4,-1,0
  4506.7    0.07       0  4618.9     0.1       0  5001.8    0.05       0
  5005.8     0.1       0
Bank Sta=5001.8,5005.8
Exp/Cntr=0.3,0.1

Chan Stop Cuts=-1