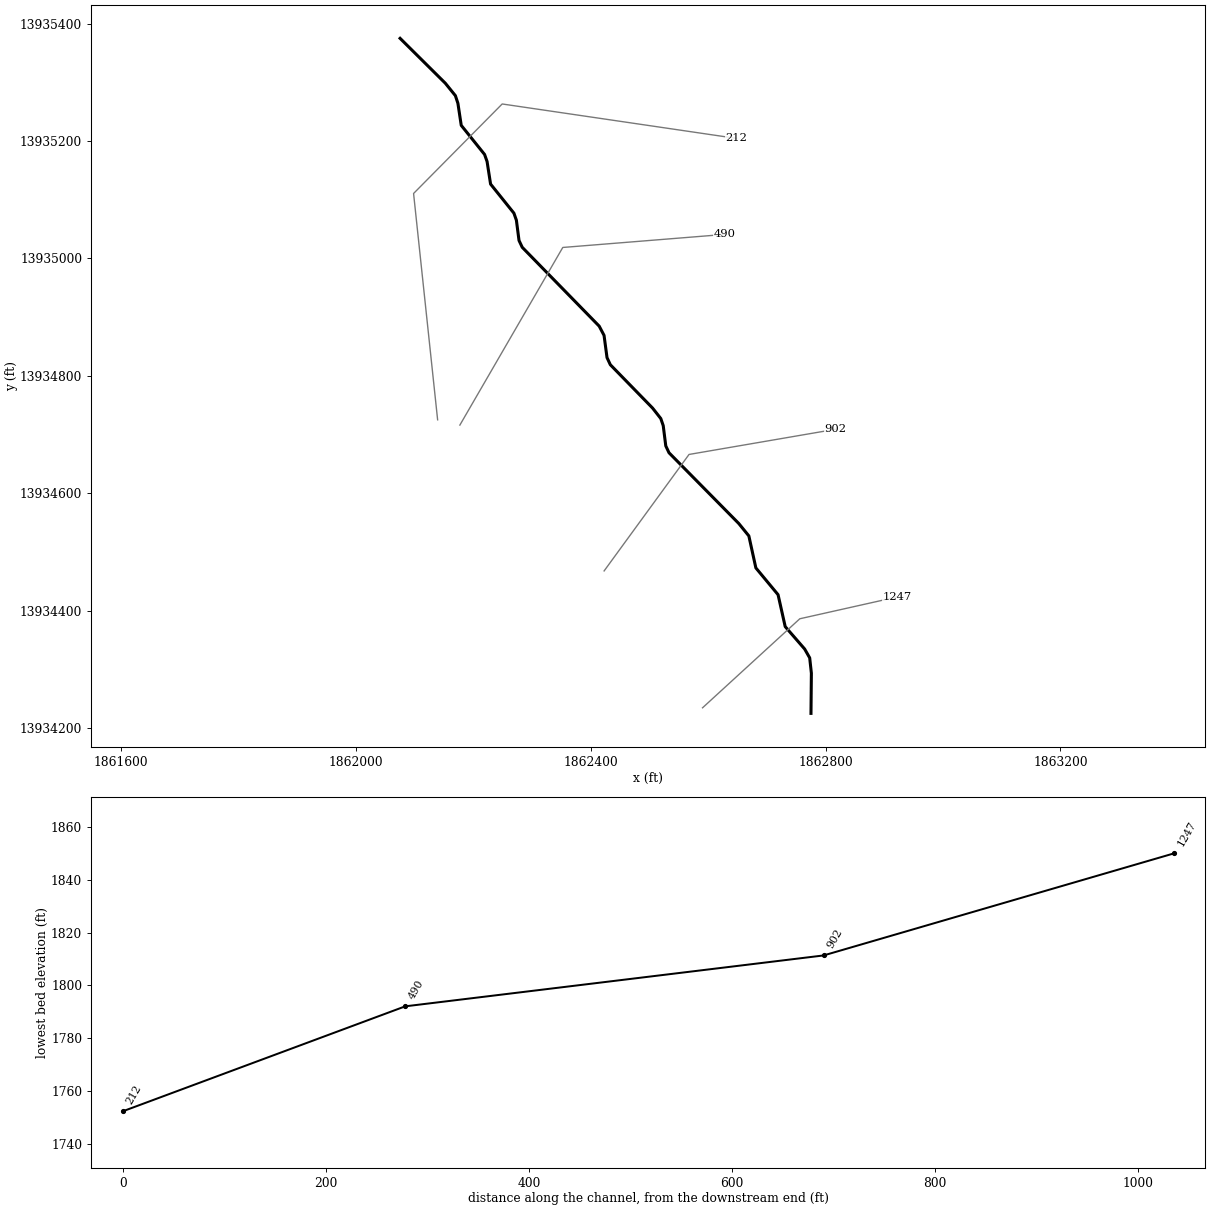
--- Stream1003.prj (project) ---

Proj Title=Stream1003 Base Level Engineering
Current Plan=p01
Default Exp/Contr=0.3,0.1
English Units
Geom File=g01
Flow File=f01
Plan File=p01
Y Axis Title=Elevation
X Axis Title(PF)=Main Channel Distance
X Axis Title(XS)=Station
BEGIN DESCRIPTION:
Stream1003
END DESCRIPTION:
DSS Export Rating Curves= 0
DSS Export Rating Curve Sorted= 0
DSS Export Volume Flow Curves= 0
DXF OffsetX= 0
DXF OffsetY= 0
DXF ScaleX= 1
DXF ScaleY= 10

--- Stream1003.p01 (plan) ---

Plan Title=Multiple Run
Short Identifier=Multiple
Geom File=g01
Flow File=f01
Subcritical Flow
K Sum by GR= 0
Std Step Tol= 0.01
Critical Tol= 0.01
Num of Std Step Trials= 20
Max Error Tol= 0.3
Flow Tol Ratio= 0.001
Split Flow NTrial= 30
Split Flow Tol= 0.02
Split Flow Ratio= 0.02
Log Output Level= 0
Friction Slope Method= 1
Unsteady Friction Slope Method= 2
Unsteady Bridges Friction Slope Method= 1
Parabolic Critical Depth
Global Vel Dist=  1 , 1 , 1
Global Log Level= 0
CheckData=True
Encroach Param= -1, 0, 0, 0
BEGIN DESCRIPTION:
Multiple Run
END DESCRIPTION:

--- Stream1003.f01 (steady flow) ---

Flow Title=Multiple
Program Version=4.10
Number of Profiles= 7
Profile Names=10-year,25-year,50-year,1pct_min,100-year,1pct_plu,500-year
River Rch & RM=Stream1003,Reach-1         ,1247
     155     232     296     185     370     738     563
Boundary for River Rch & Prof#=Stream1003,Reach-1         , 1
Up Type= 0
Dn Type= 3
Dn Slope=0.01
Boundary for River Rch & Prof#=Stream1003,Reach-1         , 2
Up Type= 0
Dn Type= 3
Dn Slope=0.01
Boundary for River Rch & Prof#=Stream1003,Reach-1         , 3
Up Type= 0
Dn Type= 3
Dn Slope=0.01
Boundary for River Rch & Prof#=Stream1003,Reach-1         , 4
Up Type= 0
Dn Type= 3
Dn Slope=0.01
Boundary for River Rch & Prof#=Stream1003,Reach-1         , 5
Up Type= 0
Dn Type= 3
Dn Slope=0.01
Boundary for River Rch & Prof#=Stream1003,Reach-1         , 6
Up Type= 0
Dn Type= 3
Dn Slope=0.01
Boundary for River Rch & Prof#=Stream1003,Reach-1         , 7
Up Type= 0
Dn Type= 3
Dn Slope=0.01
DSS Import GetInterval= 0
DSS Import GetPeak= 0
DSS Import FillOption= 0

--- Stream1003.g01 (geometry) ---

Geom Title=Existing Conditions
Program Version=4.10

River Reach=Stream1003      ,Reach-1
Reach XY= 30
        1862775.       13934225.      1862775.68     13934293.46
      1862772.81     13934319.55      1862764.21     13934334.67
      1862731.09     13934372.81      1862718.92      13934427.2
       1862681.1     13934472.81      1862669.17      13934527.3
      1862651.99     13934548.47      1862533.16     13934668.95
      1862527.64     13934680.64      1862523.29      13934715.2
      1862519.13     13934727.28      1862505.17     13934745.07
      1862433.18     13934818.96      1862427.54     13934831.05
      1862422.47     13934868.95      1862414.22     13934884.68
      1862283.14     13935018.94      1862277.61     13935030.63
      1862273.14     13935065.14       1862268.9     13935077.19
      1862229.16     13935126.72      1862223.19     13935165.16
      1862218.92      13935177.2      1862179.18     13935226.73
       1862173.5     13935264.38      1862169.21     13935277.32
      1862152.08     13935298.51        1862075.       13935375.

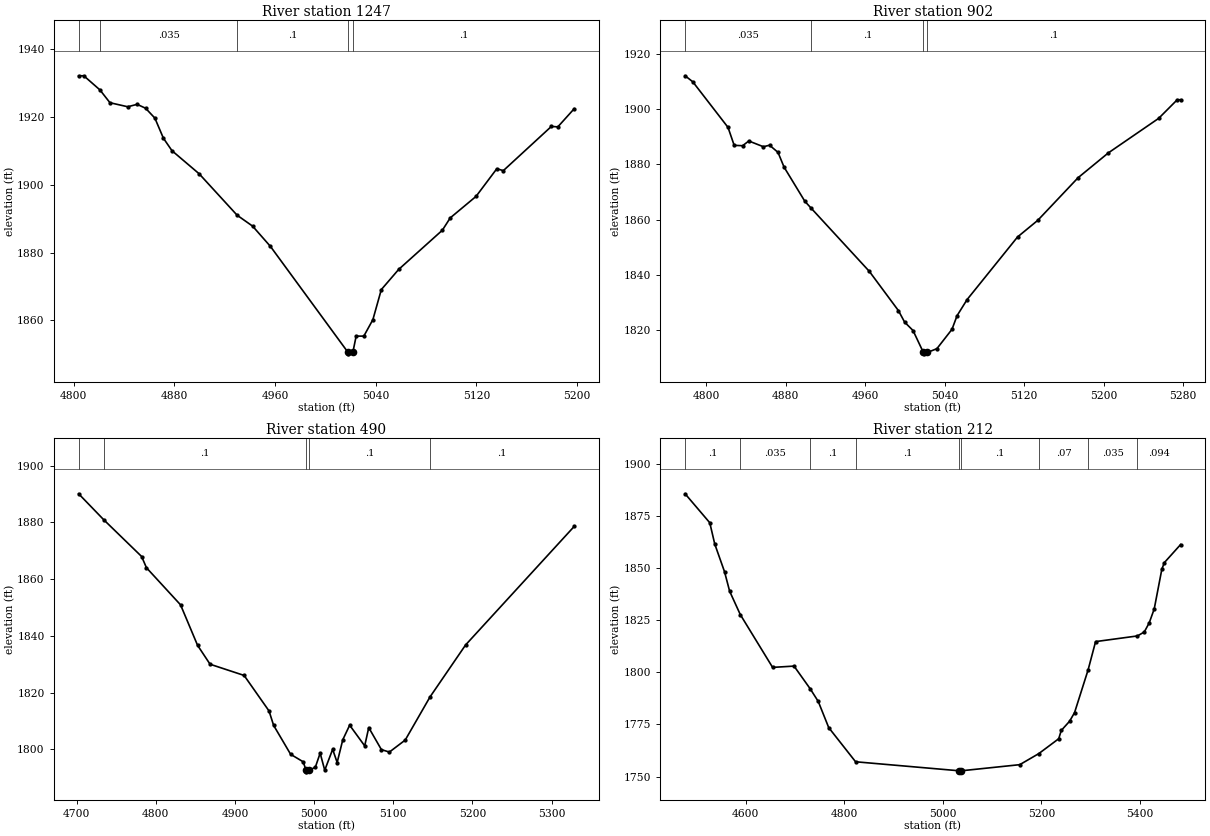
Type RM Length L Ch R = 1 ,1247    ,345,345,345
BEGIN DESCRIPTION:
Stream1003 3.0
END DESCRIPTION:
XS GIS Cut Line= 3
      1862590.26     13934234.49      1862755.93     13934386.16
      1862921.12     13934423.18
#Sta/Elev= 30
  4803.8 1932.17  4807.9 1932.17  4820.7 1928.01  4828.7 1924.22  4842.8 1923.03
  4850.3 1923.74    4857  1922.6  4864.4 1919.68  4871.2 1913.74    4878 1910.06
  4899.6 1903.25  4929.8 1891.02  4942.1  1887.8  4956.3  1881.8  5017.8 1850.62
  5018.1 1850.12  5021.8 1850.62  5024.4 1855.35  5030.5 1855.35  5037.7 1860.21
  5044.4 1869.08  5058.2 1875.03  5092.9 1886.59  5099.2 1890.24  5119.7 1896.58
  5136.2 1904.74  5141.4 1904.18  5179.6 1917.23  5184.7 1917.09  5197.7 1922.44
#Mann= 5 ,-1 , 0
  4803.8      .1       0  4820.7    .035       0  4929.8      .1       0
  5017.8     .05       0  5021.8      .1       0
Bank Sta=5017.8,5021.8
XS Rating Curve= 0 ,0
Exp/Cntr=0.3,0.1

Type RM Length L Ch R = 1 ,902     ,412,412,412
BEGIN DESCRIPTION:
Stream1003 2.0
END DESCRIPTION:
XS GIS Cut Line= 3
       1862422.6     13934467.69      1862567.24      13934666.1
      1862816.75     13934708.99
#Sta/Elev= 30
  4778.7 1912.04  4786.4 1909.88  4821.9 1893.36  4828.1 1886.86  4836.6 1886.73
  4842.8 1888.44  4857.5 1886.36  4863.7 1886.91  4872.2 1884.32  4878.3 1878.98
  4899.2 1866.62  4905.7 1864.06  4964.1 1841.25  4993.4 1827.04  4999.6 1822.89
  5008.1 1819.83  5018.5  1811.9  5018.7  1811.4  5022.5  1811.9  5032.1 1813.27
  5047.3 1820.28  5052.4 1825.21  5062.5 1831.04  5113.3 1853.71  5133.6 1859.71
  5174.2 1875.15  5204.6 1884.12  5255.3 1896.63    5274 1903.37  5277.4 1903.37
#Mann= 4 ,-1 , 0
  4778.7    .035       0  4905.7      .1       0  5018.5     .05       0
  5022.5      .1       0
Bank Sta=5018.5,5022.5
XS Rating Curve= 0 ,0
Exp/Cntr=0.3,0.1

Type RM Length L Ch R = 1 ,490     ,278,278,278
BEGIN DESCRIPTION:
Stream1003 1.0
END DESCRIPTION:
XS GIS Cut Line= 3
      1862176.86     13934716.14      1862352.17     13935018.73
      1862627.77     13935040.94
#Sta/Elev= 30
  4702.4  1890.1    4734 1880.98    4782 1867.99  4788.1 1864.03  4831.2 1850.95
  4852.7 1836.68  4868.5 1830.02  4911.5 1826.07    4943 1813.55  4948.8 1808.47
  4970.3 1798.27  4986.1 1795.64  4989.9 1792.59  4990.1 1792.09  4993.9 1792.59
  5001.6 1793.78  5007.6 1798.68  5013.4 1792.66  5023.4 1800.02  5029.1 1795.38
  5036.2  1803.4  5044.9 1808.53  5063.9 1801.24    5069 1807.68    5085 1799.92
  5095.1 1799.06  5115.1 1803.29  5146.4 1818.48  5191.4 1836.82  5328.6 1878.58
#Mann= 5 ,-1 , 0
  4702.4      .1       0    4734      .1       0  4989.9     .05       0
  4993.9      .1       0  5146.4      .1       0
Bank Sta=4989.9,4993.9
XS Rating Curve= 0 ,0
Exp/Cntr=0.3,0.1

Type RM Length L Ch R = 1 ,212     ,0,0,0
BEGIN DESCRIPTION:
Stream1003 0.0
END DESCRIPTION:
XS GIS Cut Line= 4
      1862138.95     13934725.13      1862097.98     13935110.69
      1862248.93     13935263.18      1862648.05     13935204.52
#Sta/Elev= 30
  4476.7 1885.68  4526.8 1871.78  4536.9 1861.56  4556.7  1848.3  4567.1 1838.93
  4588.7 1827.73  4654.3 1802.39  4697.8 1803.01  4730.5 1792.15  4746.9 1786.07
  4768.2 1773.49  4822.7 1757.11  5033.1 1752.78  5033.3 1752.28  5037.1 1752.78
  5155.9 1755.72  5194.5 1761.02    5235 1768.17  5240.1 1772.12    5257 1776.55
  5267.1 1780.69  5294.6 1801.19  5309.8 1814.76  5394.7 1817.48  5408.6 1819.37
  5418.7 1823.79  5428.8 1830.44  5444.3 1849.53  5449.4 1852.67  5482.4 1861.34
#Mann= 9 ,-1 , 0
  4476.7      .1       0  4588.7    .035       0  4730.5      .1       0
  4822.7      .1       0  5033.1     .05       0  5037.1      .1       0
  5194.5     .07       0  5294.6    .035       0  5394.7    .094       0
Bank Sta=5033.1,5037.1
XS Rating Curve= 0 ,0
Exp/Cntr=0.3,0.1

Chan Stop Cuts=-1
Use User Specified Reach Order=0
Composite Channel Slope=5