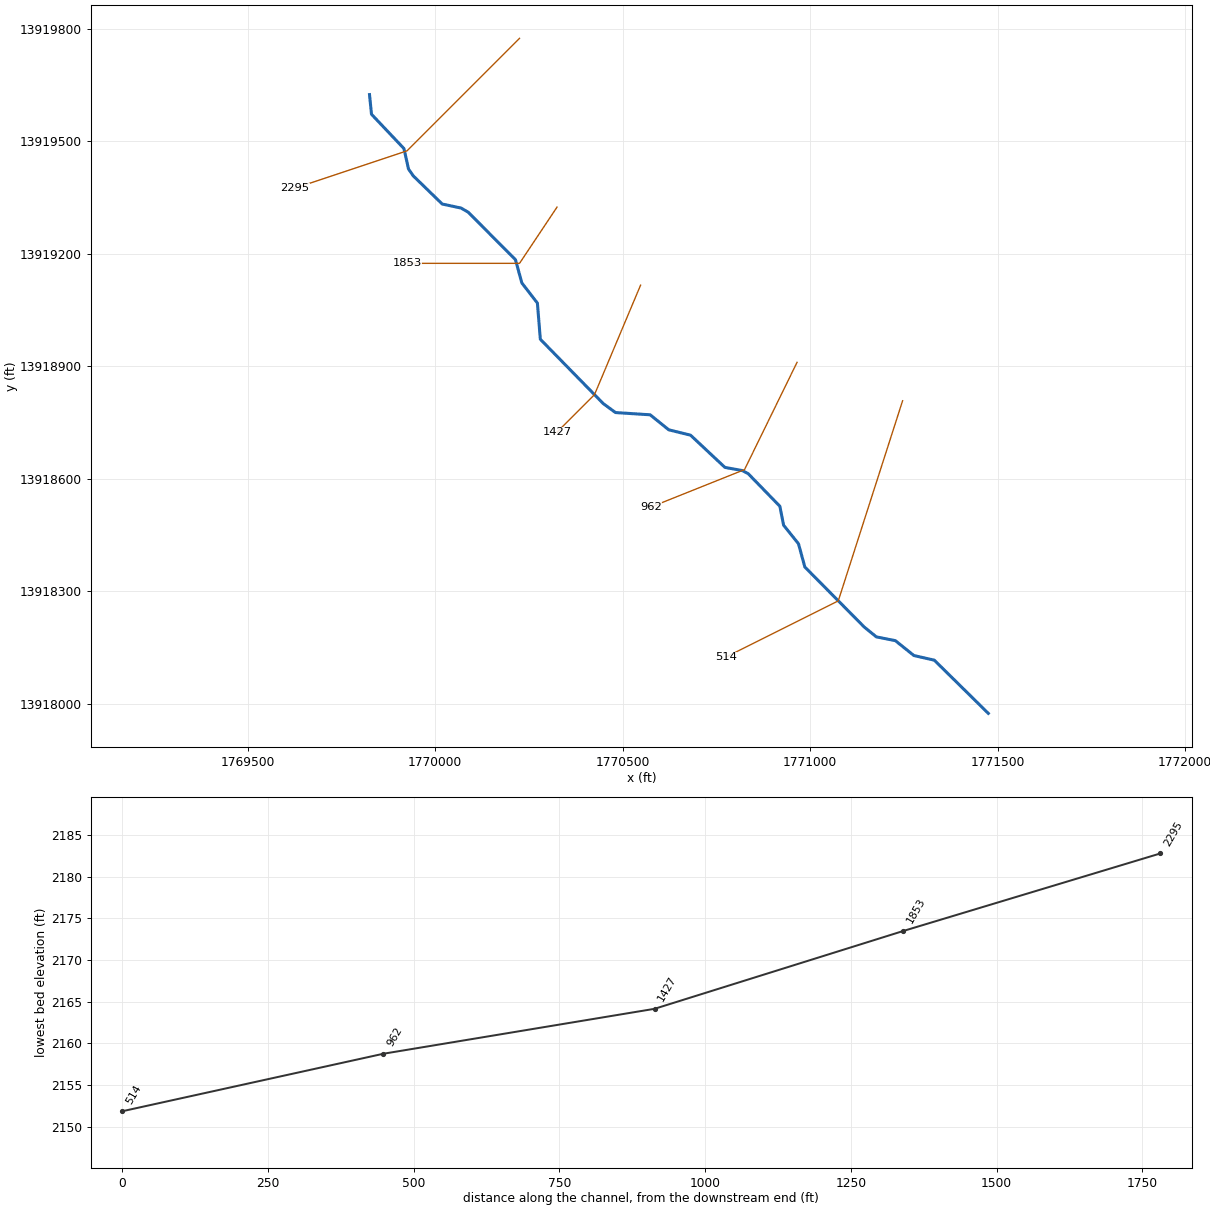
--- Stream1004.prj (project) ---

Proj Title=Stream1004 Base Level Engineering
Current Plan=p01
Default Exp/Contr=0.3,0.1
English Units
Geom File=g01
Flow File=f01
Plan File=p01
BEGIN DESCRIPTION:
Stream1004
END DESCRIPTION:

--- Stream1004.p01 (plan) ---

Plan Title=Multiple Run
Short Identifier=Multiple
Geom File=g01
Flow File=f01
Subcritical Flow
K Sum by GR= 0
Std Step Tol= 0.01
Critical Tol= 0.01
Num of Std Step Trials= 20
Max Error Tol= 0.3
Flow Tol Ratio= 0.001
Split Flow NTrial= 30
Split Flow Tol= 0.02
Split Flow Ratio= 0.02
Log Output Level= 0
Friction Slope Method= 1
Unsteady Friction Slope Method= 2
Unsteady Bridges Friction Slope Method= 1
Parabolic Critical Depth
Global Vel Dist=  1 , 1 , 1
Global Log Level= 0
CheckData=True
Encroach Param= -1, 0, 0, 0
BEGIN DESCRIPTION:
Multiple Run
END DESCRIPTION:

--- Stream1004.f01 (steady flow) ---

Flow Title=Multiple
Number of Profiles=7
Profile Names=10-year,25-year,50-year,1pct_min,100-year,1pct_plu,500-year
River Rch & RM= Stream1004,Reach-1,2295
     456     742    1002     656    1308    2611    2202
Boundary for River Rch & Prof#=Stream1004,Reach-1,1
Up Type=0
Dn Type=3
Dn Slope=0.005
Boundary for River Rch & Prof#=Stream1004,Reach-1,2
Up Type=0
Dn Type=3
Dn Slope=0.005
Boundary for River Rch & Prof#=Stream1004,Reach-1,3
Up Type=0
Dn Type=3
Dn Slope=0.005
Boundary for River Rch & Prof#=Stream1004,Reach-1,4
Up Type=0
Dn Type=3
Dn Slope=0.005
Boundary for River Rch & Prof#=Stream1004,Reach-1,5
Up Type=0
Dn Type=3
Dn Slope=0.005
Boundary for River Rch & Prof#=Stream1004,Reach-1,6
Up Type=0
Dn Type=3
Dn Slope=0.005
Boundary for River Rch & Prof#=Stream1004,Reach-1,7
Up Type=0
Dn Type=3
Dn Slope=0.005

--- Stream1004.g01 (geometry) ---

Geom Title=Existing Conditions

River Reach=Stream1004,Reach-1
Reach XY= 30
      1769825.00     13919625.00      1769830.33     13919572.49
      1769916.84     13919481.05      1769928.97     13919426.63
      1769941.64     13919408.29      1770018.93     13919333.15
      1770069.36     13919322.35      1770088.21     13919311.37
      1770214.24     13919184.68      1770231.14     13919122.83
      1770272.67     13919069.03      1770280.52     13918972.57
      1770448.13     13918801.18      1770480.89     13918777.15
      1770573.41     13918771.17      1770622.83     13918731.14
      1770681.05     13918716.84      1770772.72     13918630.87
      1770818.96     13918622.47      1770834.70     13918614.23
      1770919.17     13918527.31      1770929.19     13918476.74
      1770968.90     13918427.19      1770985.76     13918365.32
      1771144.84     13918204.61      1771176.63     13918178.95
      1771227.19     13918168.90      1771276.73     13918129.19
      1771331.06     13918116.86      1771475.00     13917975.00

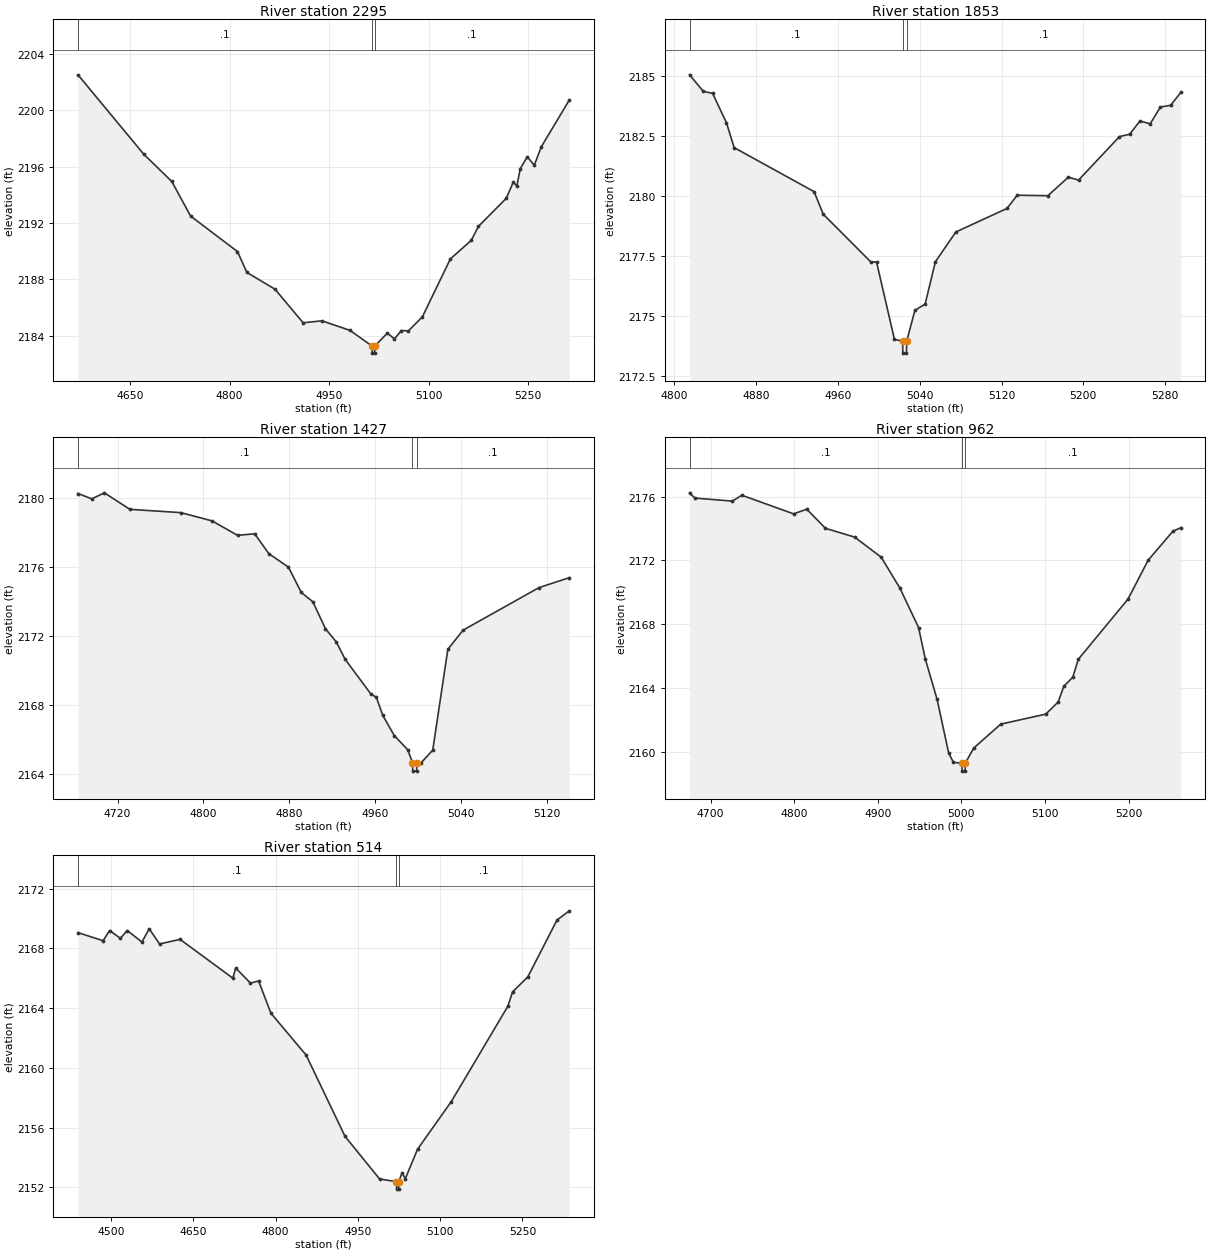
Type RM Length L Ch R = 1,2295,442,442,442
BEGIN DESCRIPTION:
Stream1004 5.0
END DESCRIPTION:
XS GIS Cut Line= 3
      1770225.00     13919775.00      1769925.00     13919475.00
      1769624.99     13919375.00
#Sta/Elev= 30
  4571.4 2202.50  4670.4 2196.88  4712.8 2194.94  4741.1 2192.49  4811.8 2189.97
  4826.0 2188.49  4868.4 2187.30  4910.8 2184.92  4939.1 2185.06  4981.5 2184.38
  5014.7 2183.27  5015.0 2182.77  5018.5 2182.77  5018.7 2183.27  5037.8 2184.19
  5048.4 2183.78  5058.9 2184.37  5069.5 2184.35  5090.5 2185.34  5132.7 2189.45
  5164.3 2190.77  5174.9 2191.75  5217.0 2193.75  5227.6 2194.90  5232.8 2194.61
  5238.1 2195.85  5248.6 2196.69  5259.2 2196.09  5269.7 2197.39  5311.9 2200.71
#Mann=3,-1,0
  4571.4     0.1       0  5014.7    0.05       0  5018.7     0.1       0
Bank Sta=5014.7,5018.7
Exp/Cntr=0.3,0.1

Type RM Length L Ch R = 1,1853,426,426,426
BEGIN DESCRIPTION:
Stream1004 4.0
END DESCRIPTION:
XS GIS Cut Line= 3
      1770325.00     13919325.00      1770225.00     13919175.00
      1769924.97     13919175.00
#Sta/Elev= 30
  4815.0 2185.04  4828.5 2184.35  4837.5 2184.27  4851.1 2183.04  4858.6 2182.01
  4936.7 2180.18  4945.7 2179.24  4992.3 2177.25  4997.8 2177.25  5015.3 2174.03
  5023.3 2173.96  5023.5 2173.46  5027.0 2173.46  5027.3 2173.96  5035.3 2175.24
  5045.3 2175.50  5055.3 2177.26  5075.3 2178.50  5125.3 2179.48  5135.3 2180.03
  5165.3 2180.01  5185.3 2180.78  5195.3 2180.66  5235.3 2182.47  5245.3 2182.57
  5255.3 2183.12  5265.3 2183.00  5275.3 2183.70  5285.3 2183.77  5295.3 2184.31
#Mann=3,-1,0
  4815.0     0.1       0  5023.3    0.05       0  5027.3     0.1       0
Bank Sta=5023.3,5027.3
Exp/Cntr=0.3,0.1

Type RM Length L Ch R = 1,1427,465,465,465
BEGIN DESCRIPTION:
Stream1004 3.0
END DESCRIPTION:
XS GIS Cut Line= 3
      1770547.81     13919116.86      1770425.00     13918825.00
      1770324.98     13918724.98
#Sta/Elev= 30
  4683.1 2180.28  4696.0 2179.97  4707.7 2180.32  4731.5 2179.36  4779.0 2179.17
  4808.1 2178.69  4831.9 2177.85  4847.9 2177.94  4861.0 2176.79  4879.4 2176.00
  4891.3 2174.53  4902.1 2173.99  4913.9 2172.42  4923.8 2171.67  4932.3 2170.64
  4956.0 2168.65  4961.4 2168.43  4967.2 2167.40  4978.0 2166.22  4990.6 2165.39
  4995.0 2164.65  4995.3 2164.15  4998.8 2164.15  4999.0 2164.65  5003.3 2164.65
  5013.9 2165.37  5028.0 2171.23  5042.2 2172.34  5112.9 2174.81  5141.2 2175.39
#Mann=3,-1,0
  4683.1     0.1       0  4995.0    0.05       0  4999.0     0.1       0
Bank Sta=4995,4999
Exp/Cntr=0.3,0.1

Type RM Length L Ch R = 1,962,448,448,448
BEGIN DESCRIPTION:
Stream1004 2.0
END DESCRIPTION:
XS GIS Cut Line= 3
      1770965.04     13918911.05      1770825.00     13918625.00
      1770574.96     13918524.98
#Sta/Elev= 30
  4674.8 2176.25  4681.1 2175.92  4726.1 2175.73  4737.3 2176.10  4799.2 2174.93
  4815.1 2175.22  4837.4 2174.02  4872.3 2173.47  4904.2 2172.20  4926.5 2170.26
  4948.8 2167.79  4956.8 2165.82  4971.0 2163.27  4984.8 2159.91  4990.5 2159.32
  5000.7 2159.27  5001.0 2158.77  5004.5 2158.77  5004.7 2159.27  5014.8 2160.22
  5047.1 2161.72  5101.0 2162.35  5115.8 2163.11  5122.5 2164.09  5133.3 2164.67
  5140.0 2165.80  5199.3 2169.57  5223.5 2172.02  5253.1 2173.84  5262.6 2174.06
#Mann=3,-1,0
  4674.8     0.1       0  5000.7    0.05       0  5004.7     0.1       0
Bank Sta=5000.7,5004.7
Exp/Cntr=0.3,0.1

Type RM Length L Ch R = 1,514,0,0,0
BEGIN DESCRIPTION:
Stream1004 1.0
END DESCRIPTION:
XS GIS Cut Line= 3
      1771246.50     13918808.59      1771075.00     13918275.00
      1770774.99     13918124.99
#Sta/Elev= 30
  4439.5 2169.06  4485.3 2168.52  4497.2 2169.20  4516.8 2168.68  4529.3 2169.20
  4556.2 2168.43  4569.3 2169.32  4588.3 2168.30  4625.6 2168.61  4721.9 2166.01
  4727.2 2166.69  4754.0 2165.68  4768.9 2165.82  4791.4 2163.66  4855.5 2160.86
  4926.4 2155.42  4989.5 2152.56  5020.3 2152.38  5020.6 2151.88  5024.1 2151.88
  5024.3 2152.38  5030.7 2152.98  5036.3 2152.57  5058.7 2154.55  5120.2 2157.74
  5223.6 2164.14  5232.0 2165.09  5259.9 2166.10  5313.0 2169.90  5335.4 2170.52
#Mann=3,-1,0
  4439.5     0.1       0  5020.3    0.05       0  5024.3     0.1       0
Bank Sta=5020.3,5024.3
Exp/Cntr=0.3,0.1

Chan Stop Cuts=-1