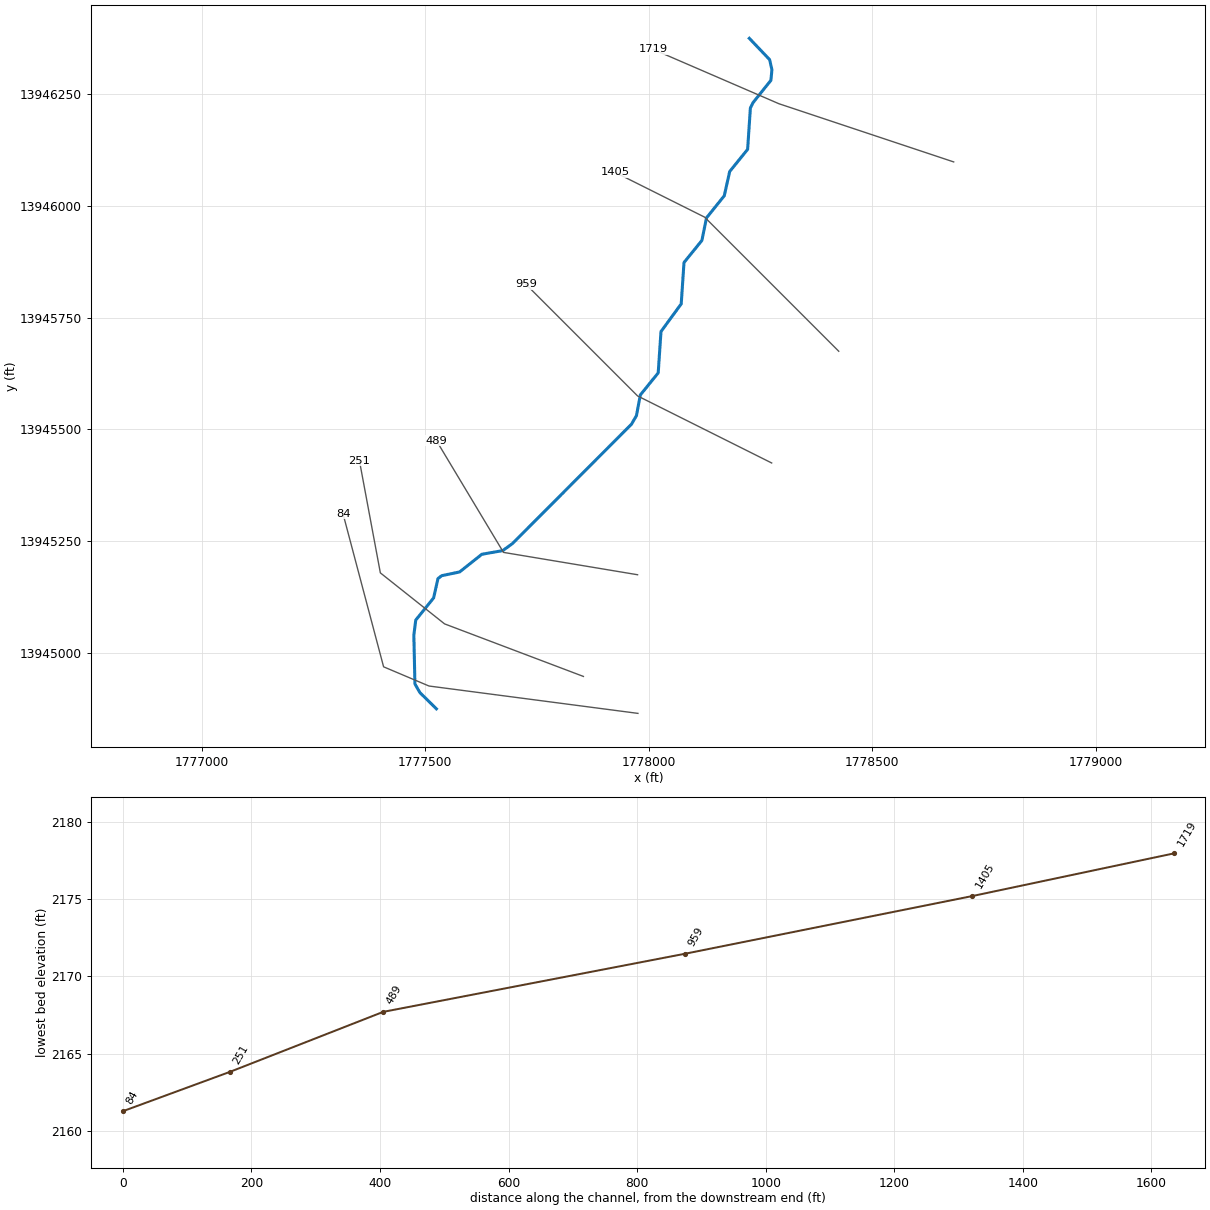
--- Stream1005.prj (project) ---

Proj Title=Stream1005 Base Level Engineering
Current Plan=p01
Default Exp/Contr=0.3,0.1
English Units
Geom File=g01
Flow File=f01
Plan File=p01
BEGIN DESCRIPTION:
Stream1005
END DESCRIPTION:

--- Stream1005.p01 (plan) ---

Plan Title=Multiple Run
Short Identifier=Multiple
Geom File=g01
Flow File=f01
Subcritical Flow
K Sum by GR= 0
Std Step Tol= 0.01
Critical Tol= 0.01
Num of Std Step Trials= 20
Max Error Tol= 0.3
Flow Tol Ratio= 0.001
Split Flow NTrial= 30
Split Flow Tol= 0.02
Split Flow Ratio= 0.02
Log Output Level= 0
Friction Slope Method= 1
Unsteady Friction Slope Method= 2
Unsteady Bridges Friction Slope Method= 1
Parabolic Critical Depth
Global Vel Dist=  1 , 1 , 1
Global Log Level= 0
CheckData=True
Encroach Param= -1, 0, 0, 0
BEGIN DESCRIPTION:
Multiple Run
END DESCRIPTION:

--- Stream1005.f01 (steady flow) ---

Flow Title=Multiple
Number of Profiles=7
Profile Names=10-year,25-year,50-year,1pct_min,100-year,1pct_plu,500-year
River Rch & RM= Stream1005,Reach-1,1719
     967    1639    2272    1522    3036    6058    5362
Boundary for River Rch & Prof#=Stream1005,Reach-1,1
Up Type=0
Dn Type=3
Dn Slope=0.005
Boundary for River Rch & Prof#=Stream1005,Reach-1,2
Up Type=0
Dn Type=3
Dn Slope=0.005
Boundary for River Rch & Prof#=Stream1005,Reach-1,3
Up Type=0
Dn Type=3
Dn Slope=0.005
Boundary for River Rch & Prof#=Stream1005,Reach-1,4
Up Type=0
Dn Type=3
Dn Slope=0.005
Boundary for River Rch & Prof#=Stream1005,Reach-1,5
Up Type=0
Dn Type=3
Dn Slope=0.005
Boundary for River Rch & Prof#=Stream1005,Reach-1,6
Up Type=0
Dn Type=3
Dn Slope=0.005
Boundary for River Rch & Prof#=Stream1005,Reach-1,7
Up Type=0
Dn Type=3
Dn Slope=0.005

--- Stream1005.g01 (geometry) ---

Geom Title=Existing Conditions

River Reach=Stream1005,Reach-1
Reach XY= 30
      1778225.00     13946375.00      1778270.39     13946327.37
      1778275.55     13946304.79      1778273.24     13946281.06
      1778233.21     13946231.06      1778227.37     13946219.04
      1778221.17     13946126.58      1778181.12     13946077.18
      1778168.92     13946022.80      1778129.16     13945973.28
      1778118.88     13945922.82      1778078.83     13945873.42
      1778072.65     13945780.97      1778027.35     13945719.03
      1778021.18     13945626.58      1777981.14     13945577.17
      1777972.50     13945531.03      1777961.38     13945511.78
      1777695.09     13945244.78      1777673.36     13945228.95
      1777626.71     13945220.82      1777576.85     13945181.24
      1777536.99     13945172.93      1777528.50     13945166.54
      1777518.72     13945123.16      1777478.73     13945073.47
      1777474.52     13945040.17      1777476.88     13944930.79
      1777487.91     13944911.50      1777525.00     13944875.00

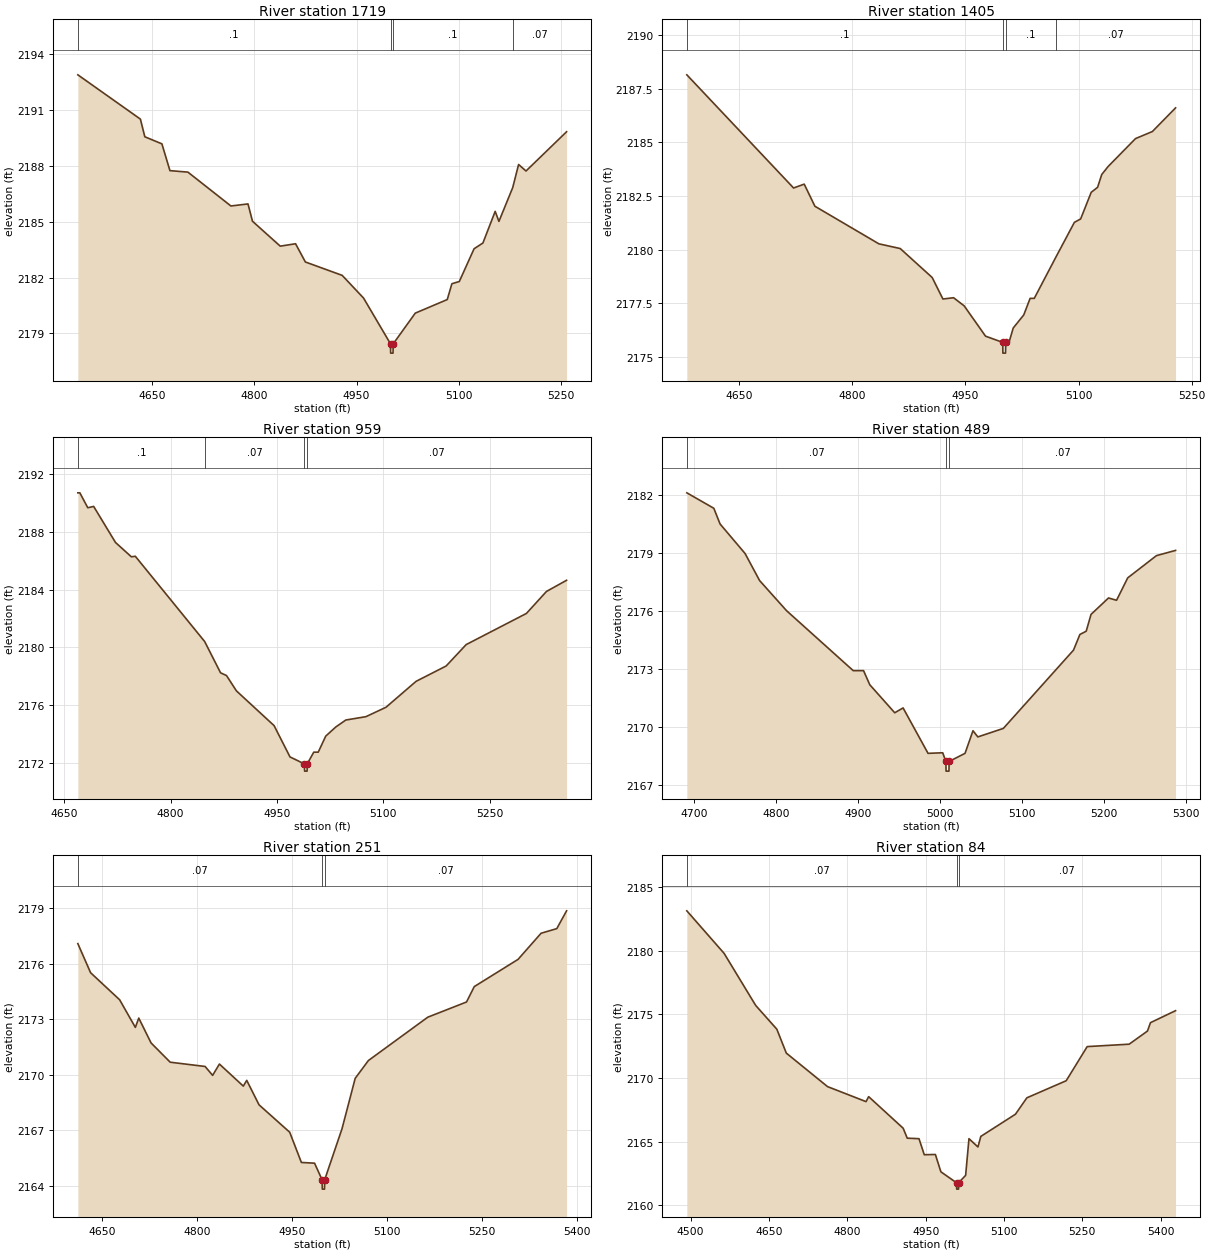
Type RM Length L Ch R = 1,1719,314,314,314
BEGIN DESCRIPTION:
Stream1005 4.0
END DESCRIPTION:
XS GIS Cut Line= 3
      1778682.18     13946098.53      1778291.30     13946228.67
      1778010.29     13946350.09
#Sta/Elev= 30
  4540.5 2192.90  4632.4 2190.52  4638.9 2189.57  4664.0 2189.19  4675.8 2187.75
  4702.2 2187.67  4765.4 2185.85  4790.5 2185.96  4797.1 2185.03  4837.9 2183.69
  4860.4 2183.82  4874.8 2182.84  4928.9 2182.12  4960.3 2180.90  4999.9 2178.44
  5000.1 2177.94  5003.6 2177.94  5003.9 2178.44  5036.3 2180.09  5083.3 2180.82
  5090.1 2181.67  5101.0 2181.79  5122.7 2183.55  5135.7 2183.86  5153.7 2185.56
  5159.2 2185.02  5179.5 2186.84  5188.1 2188.08  5199.0 2187.73  5258.6 2189.84
#Mann=4,-1,0
  4540.5     0.1       0  4999.9    0.05       0  5003.9     0.1       0
  5179.5    0.07       0
Bank Sta=4999.9,5003.9
Exp/Cntr=0.3,0.1

Type RM Length L Ch R = 1,1405,446,446,446
BEGIN DESCRIPTION:
Stream1005 3.0
END DESCRIPTION:
XS GIS Cut Line= 3
      1778425.03     13945674.97      1778125.00     13945975.00
      1777925.02     13946074.99
#Sta/Elev= 30
  4580.7 2188.14  4722.2 2182.87  4736.3 2183.05  4750.5 2182.02  4835.3 2180.27
  4863.6 2180.05  4906.0 2178.70  4920.2 2177.70  4934.3 2177.76  4948.4 2177.38
  4976.7 2175.97  4999.5 2175.68  4999.7 2175.18  5003.2 2175.18  5003.5 2175.68
  5007.8 2175.68  5013.4 2176.35  5027.4 2176.96  5035.8 2177.73  5041.3 2177.73
  5069.8 2179.64  5094.5 2181.27  5102.8 2181.43  5116.8 2182.67  5125.2 2182.90
  5130.8 2183.50  5139.2 2183.87  5175.5 2185.17  5197.9 2185.50  5228.6 2186.60
#Mann=4,-1,0
  4580.7     0.1       0  4999.5    0.05       0  5003.5     0.1       0
  5069.8    0.07       0
Bank Sta=4999.5,5003.5
Exp/Cntr=0.3,0.1

Type RM Length L Ch R = 1,959,470,470,470
BEGIN DESCRIPTION:
Stream1005 2.0
END DESCRIPTION:
XS GIS Cut Line= 3
      1778274.99     13945425.00      1777975.00     13945575.00
      1777724.97     13945825.03
#Sta/Elev= 30
  4669.2 2190.68  4672.0 2190.68  4683.2 2189.65  4691.5 2189.74  4722.3 2187.25
  4744.7 2186.26  4750.2 2186.30  4848.0 2180.41  4870.4 2178.25  4878.8 2178.06
  4892.8 2177.00  4945.9 2174.60  4968.3 2172.44  4988.6 2171.96  4988.9 2171.46
  4992.4 2171.46  4992.6 2171.96  5001.8 2172.77  5008.1 2172.77  5018.7 2173.88
  5032.9 2174.51  5047.0 2174.99  5075.3 2175.22  5103.6 2175.87  5146.0 2177.66
  5188.4 2178.72  5216.7 2180.20  5301.6 2182.35  5329.9 2183.87  5358.2 2184.64
#Mann=4,-1,0
  4669.2     0.1       0  4848.0    0.07       0  4988.6    0.05       0
  4992.6    0.07       0
Bank Sta=4988.6,4992.6
Exp/Cntr=0.3,0.1

Type RM Length L Ch R = 1,489,238,238,238
BEGIN DESCRIPTION:
Stream1005 1.0
END DESCRIPTION:
XS GIS Cut Line= 3
      1777974.99     13945175.00      1777675.00     13945225.00
      1777524.99     13945475.02
#Sta/Elev= 30
  4691.5 2182.10  4724.4 2181.30  4732.0 2180.49  4762.5 2178.96  4780.2 2177.56
  4813.1 2176.00  4894.3 2172.90  4906.9 2172.90  4914.5 2172.17  4944.9 2170.72
  4955.1 2170.97  4985.5 2168.62  5003.4 2168.65  5007.2 2168.20  5007.5 2167.70
  5011.0 2167.70  5011.2 2168.20  5030.6 2168.62  5040.3 2169.79  5046.2 2169.47
  5077.3 2169.91  5162.8 2173.96  5170.6 2174.77  5178.3 2174.94  5184.2 2175.81
  5205.5 2176.66  5215.3 2176.54  5228.9 2177.70  5263.9 2178.85  5287.2 2179.12
#Mann=3,-1,0
  4691.5    0.07       0  5007.2    0.05       0  5011.2    0.07       0
Bank Sta=5007.2,5011.2
Exp/Cntr=0.3,0.1

Type RM Length L Ch R = 1,251,167,167,167
BEGIN DESCRIPTION:
Stream1005 0.0
END DESCRIPTION:
XS GIS Cut Line= 4
      1777853.84     13944947.50      1777543.23     13945065.06
      1777399.56     13945179.17      1777352.74     13945430.16
#Sta/Elev= 30
  4612.0 2177.08  4632.1 2175.51  4677.9 2174.05  4702.7 2172.56  4708.1 2173.06
  4727.5 2171.72  4757.7 2170.68  4812.7 2170.45  4824.6 2169.97  4835.3 2170.58
  4873.0 2169.39  4878.4 2169.70  4897.8 2168.38  4946.2 2166.90  4964.6 2165.27
  4985.4 2165.23  4997.3 2164.33  4997.6 2163.83  5001.1 2163.83  5001.3 2164.33
  5028.7 2167.09  5049.5 2169.81  5070.3 2170.77  5164.0 2173.11  5225.1 2173.93
  5237.3 2174.76  5306.4 2176.23  5342.7 2177.64  5367.5 2177.89  5382.9 2178.85
#Mann=3,-1,0
  4612.0    0.07       0  4997.3    0.05       0  5001.3    0.07       0
Bank Sta=4997.3,5001.3
Exp/Cntr=0.3,0.1

Type RM Length L Ch R = 1,84,0,0,0
BEGIN DESCRIPTION:
Stream1005 0.1
END DESCRIPTION:
XS GIS Cut Line= 4
      1777975.83     13944864.86      1777508.38     13944926.06
      1777406.82     13944969.03      1777316.04     13945311.38
#Sta/Elev= 30
  4492.7 2183.13  4564.1 2179.79  4624.6 2175.70  4665.0 2173.84  4683.2 2171.96
  4762.1 2169.33  4835.9 2168.15  4840.9 2168.54  4907.0 2166.06  4914.8 2165.28
  4937.3 2165.24  4947.4 2163.98  4968.7 2164.00  4979.2 2162.64  5009.2 2161.78
  5009.5 2161.28  5013.0 2161.28  5013.2 2161.78  5026.6 2162.36  5033.0 2165.24
  5050.2 2164.59  5055.7 2165.42  5122.0 2167.16  5143.9 2168.45  5219.2 2169.79
  5259.4 2172.47  5339.8 2172.66  5374.8 2173.69  5380.6 2174.35  5428.6 2175.29
#Mann=3,-1,0
  4492.7    0.07       0  5009.2    0.05       0  5013.2    0.07       0
Bank Sta=5009.2,5013.2
Exp/Cntr=0.3,0.1

Chan Stop Cuts=-1