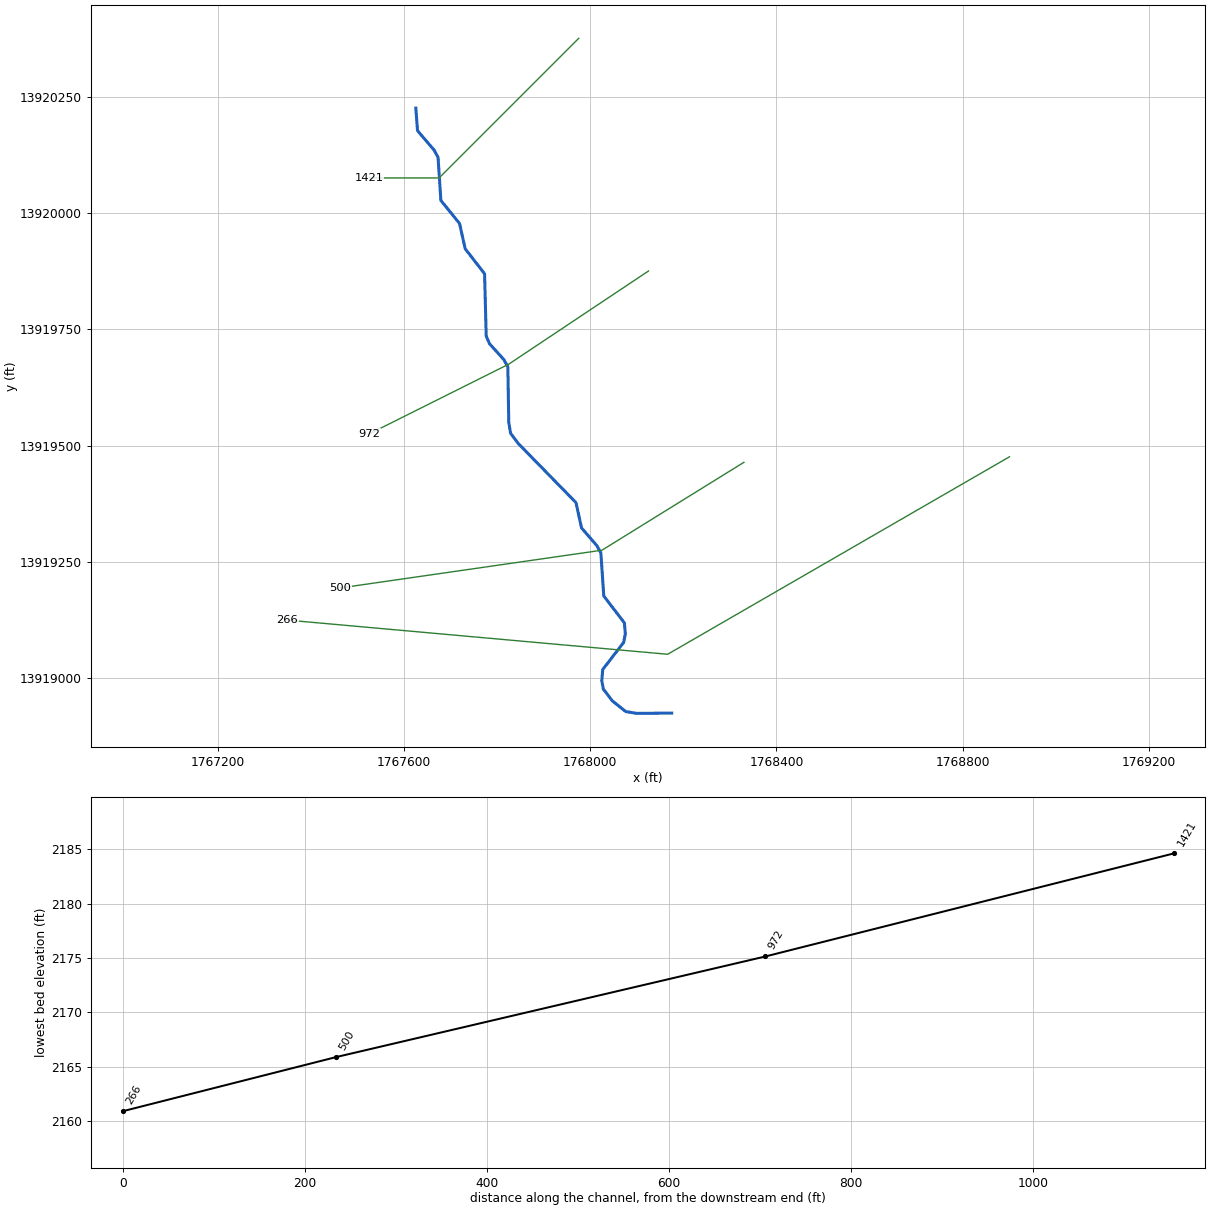
--- Stream1006.prj (project) ---

Proj Title=Stream1006 Base Level Engineering
Current Plan=p01
Default Exp/Contr=0.3,0.1
English Units
Geom File=g01
Flow File=f01
Plan File=p01
BEGIN DESCRIPTION:
Stream1006
END DESCRIPTION:

--- Stream1006.p01 (plan) ---

Plan Title=Multiple Run
Short Identifier=Multiple
Geom File=g01
Flow File=f01
Subcritical Flow
K Sum by GR= 0
Std Step Tol= 0.01
Critical Tol= 0.01
Num of Std Step Trials= 20
Max Error Tol= 0.3
Flow Tol Ratio= 0.001
Split Flow NTrial= 30
Split Flow Tol= 0.02
Split Flow Ratio= 0.02
Log Output Level= 0
Friction Slope Method= 1
Unsteady Friction Slope Method= 2
Unsteady Bridges Friction Slope Method= 1
Parabolic Critical Depth
Global Vel Dist=  1 , 1 , 1
Global Log Level= 0
CheckData=True
Encroach Param= -1, 0, 0, 0
BEGIN DESCRIPTION:
Multiple Run
END DESCRIPTION:

--- Stream1006.f01 (steady flow) ---

Flow Title=Multiple
Number of Profiles=7
Profile Names=10-year,25-year,50-year,1pct_min,100-year,1pct_plu,500-year
River Rch & RM= Stream1006,Reach-1,1421
     497     814    1103     725    1446    2886    2454
Boundary for River Rch & Prof#=Stream1006,Reach-1,1
Up Type=0
Dn Type=3
Dn Slope=0.005
Boundary for River Rch & Prof#=Stream1006,Reach-1,2
Up Type=0
Dn Type=3
Dn Slope=0.005
Boundary for River Rch & Prof#=Stream1006,Reach-1,3
Up Type=0
Dn Type=3
Dn Slope=0.005
Boundary for River Rch & Prof#=Stream1006,Reach-1,4
Up Type=0
Dn Type=3
Dn Slope=0.005
Boundary for River Rch & Prof#=Stream1006,Reach-1,5
Up Type=0
Dn Type=3
Dn Slope=0.005
Boundary for River Rch & Prof#=Stream1006,Reach-1,6
Up Type=0
Dn Type=3
Dn Slope=0.005
Boundary for River Rch & Prof#=Stream1006,Reach-1,7
Up Type=0
Dn Type=3
Dn Slope=0.005

--- Stream1006.g01 (geometry) ---

Geom Title=Existing Conditions

River Reach=Stream1006,Reach-1
Reach XY= 30
      1767625.00     13920225.00      1767628.64     13920176.51
      1767664.39     13920134.75      1767672.77     13920119.08
      1767678.82     13920026.58      1767718.89     13919977.18
      1767731.12     13919922.82      1767772.75     13919869.07
      1767776.23     13919735.51      1767783.15     13919718.95
      1767814.14     13919684.65      1767822.73     13919669.06
      1767824.73     13919549.89      1767828.54     13919526.47
      1767844.61     13919504.84      1767969.17     13919377.30
      1767981.14     13919322.83      1768014.16     13919284.65
      1768022.67     13919269.03      1768028.89     13919176.58
      1768073.18     13919118.88      1768075.27     13919095.17
      1768071.60     13919076.72      1768026.79     13919018.84
      1768024.55     13918995.02      1768028.01     13918976.40
      1768047.46     13918951.04      1768076.08     13918928.28
      1768099.62     13918924.36      1768175.00     13918925.00

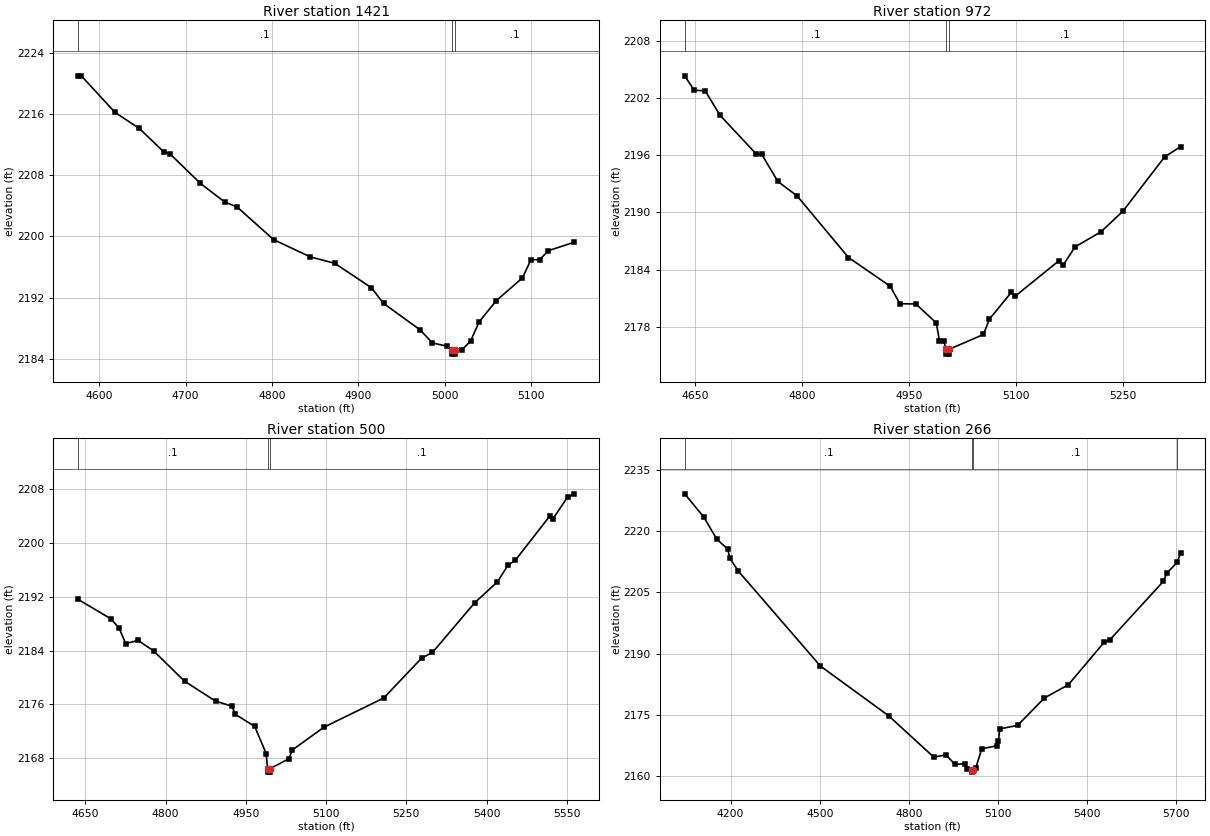
Type RM Length L Ch R = 1,1421,449,449,449
BEGIN DESCRIPTION:
Stream1006 3.0
END DESCRIPTION:
XS GIS Cut Line= 3
      1767975.02     13920375.02      1767675.00     13920075.00
      1767524.99     13920075.00
#Sta/Elev= 30
  4575.7 2220.97  4579.3 2220.97  4618.2 2216.20  4646.4 2214.10  4674.7 2211.05
  4681.8 2210.80  4717.2 2206.92  4745.4 2204.49  4759.6 2203.85  4802.0 2199.58
  4844.4 2197.33  4872.7 2196.49  4915.1 2193.31  4929.3 2191.25  4971.7 2187.79
  4985.9 2186.09  5002.5 2185.67  5008.0 2185.13  5008.2 2184.63  5011.7 2184.63
  5012.0 2185.13  5020.0 2185.21  5030.0 2186.31  5040.0 2188.86  5060.0 2191.63
  5090.0 2194.57  5100.0 2196.96  5110.0 2196.95  5120.0 2198.13  5150.0 2199.24
#Mann=3,-1,0
  4575.7     0.1       0  5008.0    0.05       0  5012.0     0.1       0
Bank Sta=5008,5012
Exp/Cntr=0.3,0.1

Type RM Length L Ch R = 1,972,472,472,472
BEGIN DESCRIPTION:
Stream1006 2.0
END DESCRIPTION:
XS GIS Cut Line= 3
      1768125.01     13919875.01      1767825.00     13919675.00
      1767524.98     13919524.99
#Sta/Elev= 30
  4635.3 2204.30  4648.8 2202.78  4663.9 2202.74  4684.9 2200.17  4736.0 2196.09
  4743.5 2196.07  4766.0 2193.24  4793.1 2191.72  4865.2 2185.27  4923.8 2182.26
  4937.3 2180.43  4959.8 2180.40  4988.4 2178.42  4992.9 2176.54  4998.7 2176.54
  5002.3 2175.65  5002.5 2175.15  5006.0 2175.15  5006.3 2175.65  5054.6 2177.21
  5063.0 2178.82  5093.7 2181.62  5099.3 2181.23  5160.8 2184.95  5166.4 2184.46
  5183.1 2186.38  5219.5 2187.96  5250.2 2190.11  5308.9 2195.81  5331.3 2196.88
#Mann=3,-1,0
  4635.3     0.1       0  5002.3    0.05       0  5006.3     0.1       0
Bank Sta=5002.3,5006.3
Exp/Cntr=0.3,0.1

Type RM Length L Ch R = 1,500,234,234,234
BEGIN DESCRIPTION:
Stream1006 1.0
END DESCRIPTION:
XS GIS Cut Line= 3
      1768330.10     13919463.91      1768025.00     13919275.00
      1767462.86     13919193.96
#Sta/Elev= 30
  4636.8 2191.61  4698.5 2188.69  4713.4 2187.30  4725.6 2185.03  4748.7 2185.51
  4777.6 2183.95  4835.5 2179.43  4893.4 2176.47  4924.2 2175.70  4930.1 2174.52
  4966.7 2172.69  4988.0 2168.66  4990.7 2166.39  4991.0 2165.89  4994.5 2165.89
  4994.7 2166.39  5030.9 2167.89  5036.1 2169.14  5096.2 2172.59  5207.8 2176.93
  5278.5 2182.87  5298.8 2183.71  5377.8 2191.12  5420.0 2194.21  5440.2 2196.74
  5453.3 2197.41  5518.6 2204.09  5523.7 2203.58  5551.3 2206.86  5563.6 2207.34
#Mann=3,-1,0
  4636.8     0.1       0  4990.7    0.05       0  4994.7     0.1       0
Bank Sta=4990.7,4994.7
Exp/Cntr=0.3,0.1

Type RM Length L Ch R = 1,266,0,0,0
BEGIN DESCRIPTION:
Stream1006 0.0
END DESCRIPTION:
XS GIS Cut Line= 3
      1768900.82     13919475.80      1768166.19     13919051.38
      1767348.30     13919124.85
#Sta/Elev= 30
  4045.4 2229.16  4109.9 2223.45  4153.6 2218.02  4190.7 2215.60  4196.7 2213.46
  4225.4 2210.26  4502.5 2186.92  4732.2 2174.73  4883.6 2164.62  4925.1 2165.14
  4955.2 2162.83  4990.3 2162.98  4995.4 2161.79  5013.5 2161.42  5013.7 2160.92
  5017.5 2161.42  5025.5 2161.98  5045.6 2166.64  5095.8 2167.38  5101.4 2168.47
  5106.4 2171.54  5166.1 2172.37  5256.5 2179.11  5336.8 2182.33  5457.3 2192.74
  5477.3 2193.40  5656.9 2207.70  5668.1 2209.65  5703.7 2212.41  5715.0 2214.68
#Mann=4,-1,0
  4045.4     0.1       0  5013.5    0.05       0  5017.5     0.1       0
  5703.7    0.07       0
Bank Sta=5013.5,5017.5
Exp/Cntr=0.3,0.1

Chan Stop Cuts=-1