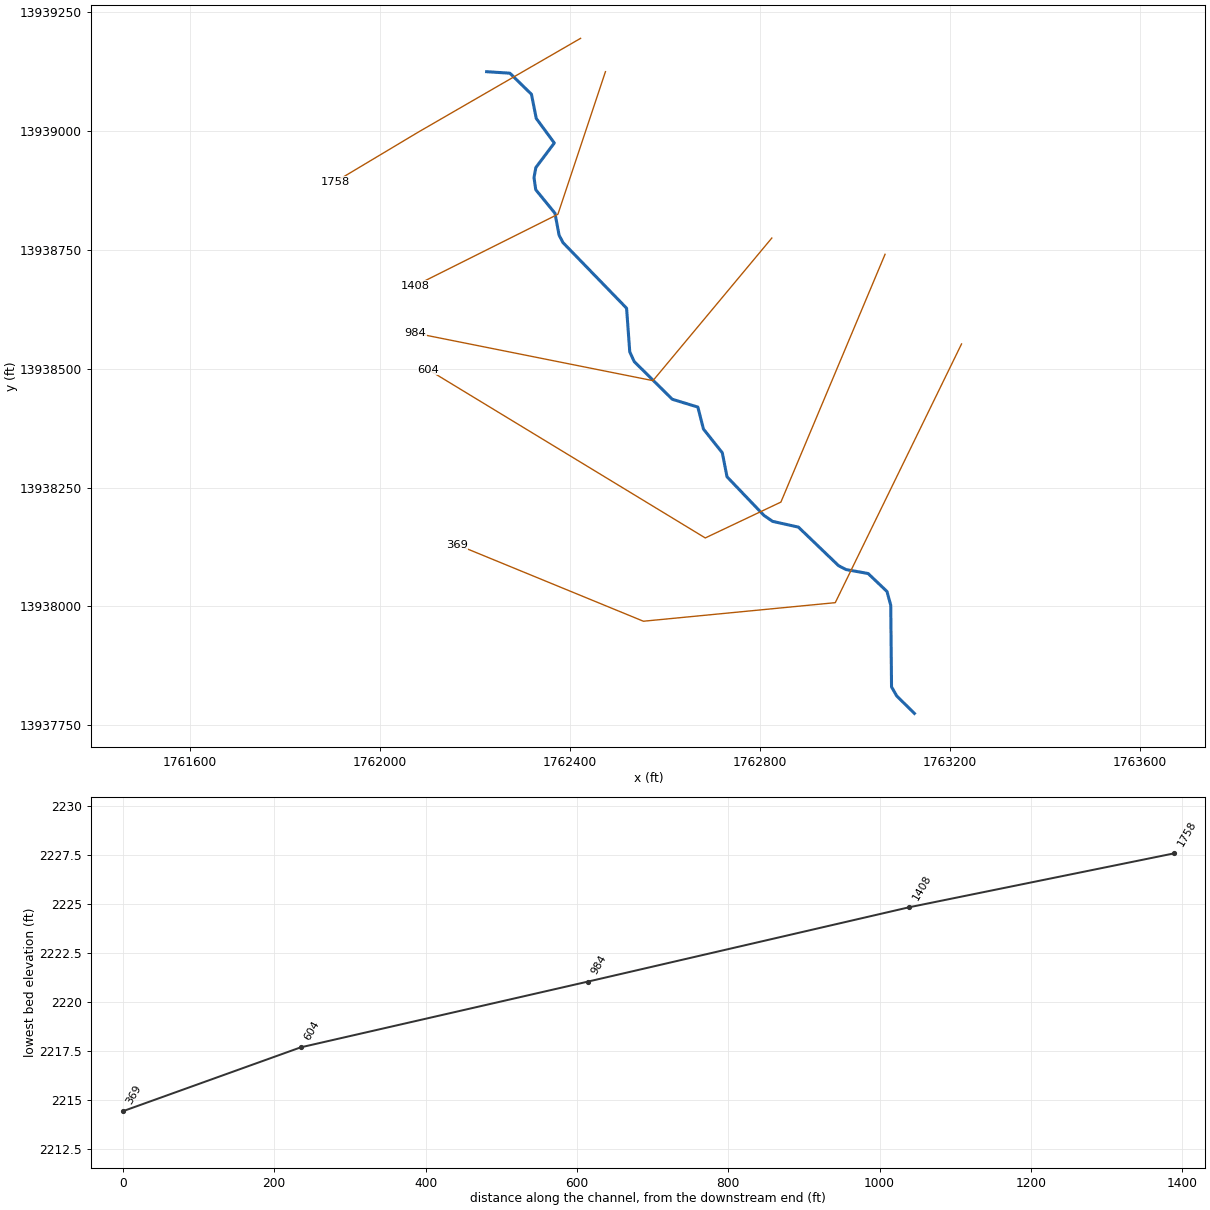
--- Stream1009.prj (project) ---

Proj Title=Stream1009 Base Level Engineering
Current Plan=p01
Default Exp/Contr=0.3,0.1
English Units
Geom File=g01
Flow File=f01
Plan File=p01
BEGIN DESCRIPTION:
Stream1009
END DESCRIPTION:

--- Stream1009.p01 (plan) ---

Plan Title=Multiple Run
Short Identifier=Multiple
Geom File=g01
Flow File=f01
Subcritical Flow
K Sum by GR= 0
Std Step Tol= 0.01
Critical Tol= 0.01
Num of Std Step Trials= 20
Max Error Tol= 0.3
Flow Tol Ratio= 0.001
Split Flow NTrial= 30
Split Flow Tol= 0.02
Split Flow Ratio= 0.02
Log Output Level= 0
Friction Slope Method= 1
Unsteady Friction Slope Method= 2
Unsteady Bridges Friction Slope Method= 1
Parabolic Critical Depth
Global Vel Dist=  1 , 1 , 1
Global Log Level= 0
CheckData=True
Encroach Param= -1, 0, 0, 0
BEGIN DESCRIPTION:
Multiple Run
END DESCRIPTION:

--- Stream1009.f01 (steady flow) ---

Flow Title=Multiple
Number of Profiles=7
Profile Names=10-year,25-year,50-year,1pct_min,100-year,1pct_plu,500-year
River Rch & RM= Stream1009,Reach-1,1758
     867    1469    2035    1362    2719    5424    4798
Boundary for River Rch & Prof#=Stream1009,Reach-1,1
Up Type=0
Dn Type=3
Dn Slope=0.005
Boundary for River Rch & Prof#=Stream1009,Reach-1,2
Up Type=0
Dn Type=3
Dn Slope=0.005
Boundary for River Rch & Prof#=Stream1009,Reach-1,3
Up Type=0
Dn Type=3
Dn Slope=0.005
Boundary for River Rch & Prof#=Stream1009,Reach-1,4
Up Type=0
Dn Type=3
Dn Slope=0.005
Boundary for River Rch & Prof#=Stream1009,Reach-1,5
Up Type=0
Dn Type=3
Dn Slope=0.005
Boundary for River Rch & Prof#=Stream1009,Reach-1,6
Up Type=0
Dn Type=3
Dn Slope=0.005
Boundary for River Rch & Prof#=Stream1009,Reach-1,7
Up Type=0
Dn Type=3
Dn Slope=0.005

--- Stream1009.g01 (geometry) ---

Geom Title=Existing Conditions

River Reach=Stream1009,Reach-1
Reach XY= 30
      1762225.00     13939125.00      1762273.97     13939121.86
      1762319.35     13939077.51      1762329.44     13939026.66
      1762367.44     13938975.00      1762328.60     13938923.36
      1762324.71     13938902.23      1762328.37     13938876.73
      1762368.82     13938827.19      1762377.49     13938781.04
      1762385.76     13938765.32      1762519.48     13938627.43
      1762526.16     13938535.48      1762535.51     13938515.19
      1762615.56     13938435.88      1762669.41     13938419.39
      1762681.24     13938373.15      1762720.82     13938323.29
      1762730.83     13938272.69      1762808.29     13938191.64
      1762826.64     13938178.97      1762881.04     13938166.82
      1762965.35     13938085.81      1762981.09     13938077.56
      1763027.58     13938069.26      1763067.31     13938031.48
      1763075.24     13938002.45      1763076.89     13937830.78
      1763087.92     13937811.50      1763125.00     13937775.00

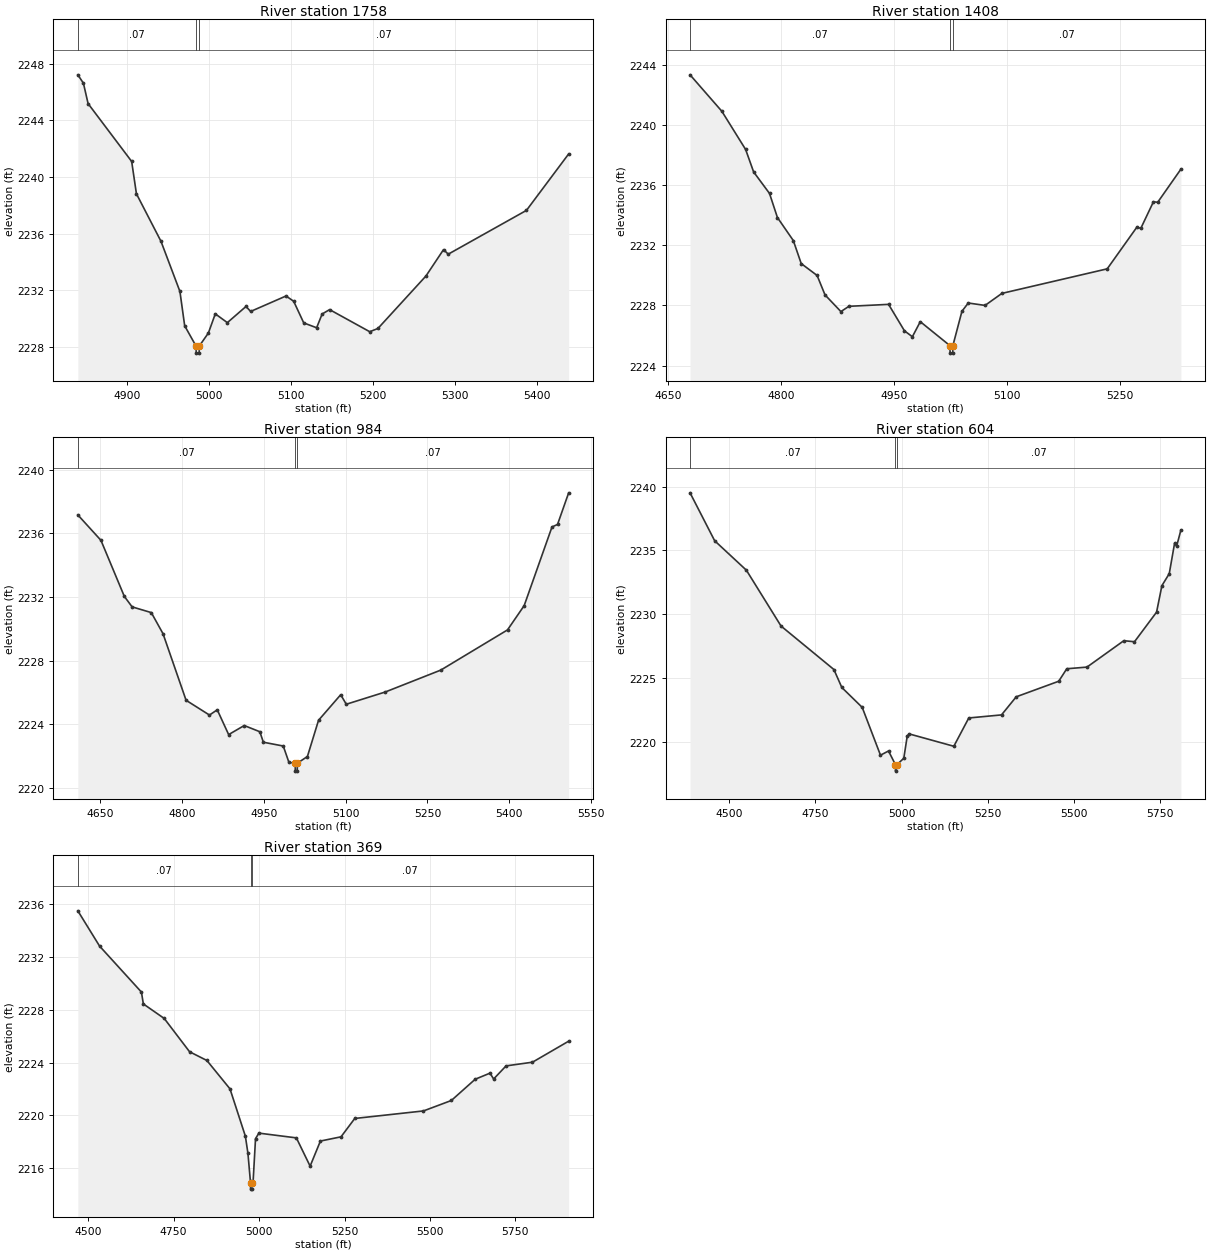
Type RM Length L Ch R = 1,1758,350,350,350
BEGIN DESCRIPTION:
Stream1009 3.0
END DESCRIPTION:
XS GIS Cut Line= 3
      1762422.73     13939195.18      1762080.48     13938997.41
      1761906.42     13938893.31
#Sta/Elev= 30
  4840.3 2247.21  4847.1 2246.62  4852.8 2245.18  4905.9 2241.10  4911.7 2238.82
  4941.6 2235.47  4964.7 2231.93  4970.5 2229.51  4984.3 2228.08  4984.6 2227.58
  4988.1 2227.58  4988.3 2228.08  4999.4 2229.00  5007.8 2230.35  5022.5 2229.73
  5045.2 2230.87  5050.9 2230.52  5094.0 2231.61  5103.3 2231.24  5115.6 2229.71
  5131.3 2229.37  5138.0 2230.34  5147.1 2230.65  5196.0 2229.09  5206.0 2229.32
  5264.5 2233.02  5285.9 2234.88  5291.7 2234.56  5387.0 2237.65  5438.4 2241.63
#Mann=3,-1,0
  4840.3    0.07       0  4984.3    0.05       0  4988.3    0.07       0
Bank Sta=4984.3,4988.3
Exp/Cntr=0.3,0.1

Type RM Length L Ch R = 1,1408,424,424,424
BEGIN DESCRIPTION:
Stream1009 2.0
END DESCRIPTION:
XS GIS Cut Line= 3
      1762475.01     13939125.04      1762375.00     13938825.00
      1762074.99     13938674.99
#Sta/Elev= 30
  4679.1 2243.32  4721.3 2240.90  4752.9 2238.36  4763.5 2236.87  4784.6 2235.44
  4795.1 2233.84  4816.2 2232.31  4826.7 2230.78  4847.8 2229.99  4858.3 2228.70
  4879.4 2227.59  4890.0 2227.94  4942.7 2228.07  4963.8 2226.31  4974.3 2225.92
  4984.8 2226.92  5024.1 2225.33  5024.4 2224.83  5027.9 2224.83  5028.1 2225.33
  5040.1 2227.61  5048.5 2228.16  5070.8 2228.00  5093.2 2228.80  5233.0 2230.43
  5272.1 2233.18  5277.7 2233.13  5294.4 2234.89  5300.0 2234.85  5330.8 2237.05
#Mann=3,-1,0
  4679.1    0.07       0  5024.1    0.05       0  5028.1    0.07       0
Bank Sta=5024.1,5028.1
Exp/Cntr=0.3,0.1

Type RM Length L Ch R = 1,984,380,380,380
BEGIN DESCRIPTION:
Stream1009 1.0
END DESCRIPTION:
XS GIS Cut Line= 3
      1762825.03     13938775.04      1762575.00     13938475.00
      1762074.96     13938575.01
#Sta/Elev= 30
  4608.6 2237.17  4651.0 2235.57  4693.9 2232.04  4708.2 2231.38  4743.4 2231.02
  4764.9 2229.69  4807.2 2225.50  4850.1 2224.57  4864.4 2224.90  4885.3 2223.34
  4913.9 2223.91  4942.5 2223.52  4949.0 2222.86  4985.5 2222.62  4995.9 2221.59
  5007.4 2221.54  5007.6 2221.04  5011.1 2221.04  5011.4 2221.54  5029.8 2221.96
  5050.2 2224.24  5090.9 2225.85  5101.1 2225.25  5172.5 2226.02  5274.5 2227.40
  5396.9 2229.93  5427.5 2231.46  5478.5 2236.41  5488.7 2236.57  5509.1 2238.56
#Mann=3,-1,0
  4608.6    0.07       0  5007.4    0.05       0  5011.4    0.07       0
Bank Sta=5007.4,5011.4
Exp/Cntr=0.3,0.1

Type RM Length L Ch R = 1,604,235,235,235
BEGIN DESCRIPTION:
Stream1009 0.0
END DESCRIPTION:
XS GIS Cut Line= 4
      1763063.27     13938740.84      1762844.15     13938219.51
      1762685.03     13938144.09      1762102.24     13938498.15
#Sta/Elev= 30
  4386.3 2239.51  4457.7 2235.75  4549.7 2233.44  4650.2 2229.06  4803.5 2225.65
  4826.5 2224.24  4885.6 2222.68  4938.6 2218.93  4961.9 2219.26  4982.1 2218.18
  4982.3 2217.68  4986.1 2218.18  5006.2 2218.69  5016.2 2220.43  5021.7 2220.60
  5151.3 2219.63  5194.7 2221.85  5289.6 2222.09  5332.3 2223.51  5455.5 2224.73
  5478.9 2225.71  5537.5 2225.84  5644.3 2227.91  5675.3 2227.83  5739.3 2230.15
  5754.8 2232.23  5776.1 2233.17  5791.6 2235.56  5797.4 2235.32  5809.8 2236.58
#Mann=3,-1,0
  4386.3    0.07       0  4982.1    0.05       0  4986.1    0.07       0
Bank Sta=4982.1,4986.1
Exp/Cntr=0.3,0.1

Type RM Length L Ch R = 1,369,0,0,0
BEGIN DESCRIPTION:
Stream1009 0.1
END DESCRIPTION:
XS GIS Cut Line= 4
      1763224.15     13938552.17      1762958.53     13938007.92
      1762554.89     13937968.86      1762162.06     13938130.15
#Sta/Elev= 30
  4469.9 2235.49  4533.5 2232.82  4655.9 2229.34  4661.6 2228.44  4722.7 2227.34
  4796.8 2224.82  4847.4 2224.16  4915.0 2222.01  4960.0 2218.43  4967.5 2217.13
  4975.0 2214.92  4975.3 2214.42  4978.8 2214.42  4979.0 2214.92  4982.6 2214.97
  4989.7 2218.24  4999.5 2218.66  5109.2 2218.30  5149.4 2216.16  5179.5 2218.06
  5239.8 2218.38  5280.0 2219.77  5481.0 2220.34  5562.5 2221.13  5632.3 2222.74
  5675.5 2223.20  5686.3 2222.76  5722.6 2223.75  5799.9 2224.03  5905.7 2225.62
#Mann=3,-1,0
  4469.9    0.07       0  4975.0    0.05       0  4979.0    0.07       0
Bank Sta=4975,4979
Exp/Cntr=0.3,0.1

Chan Stop Cuts=-1