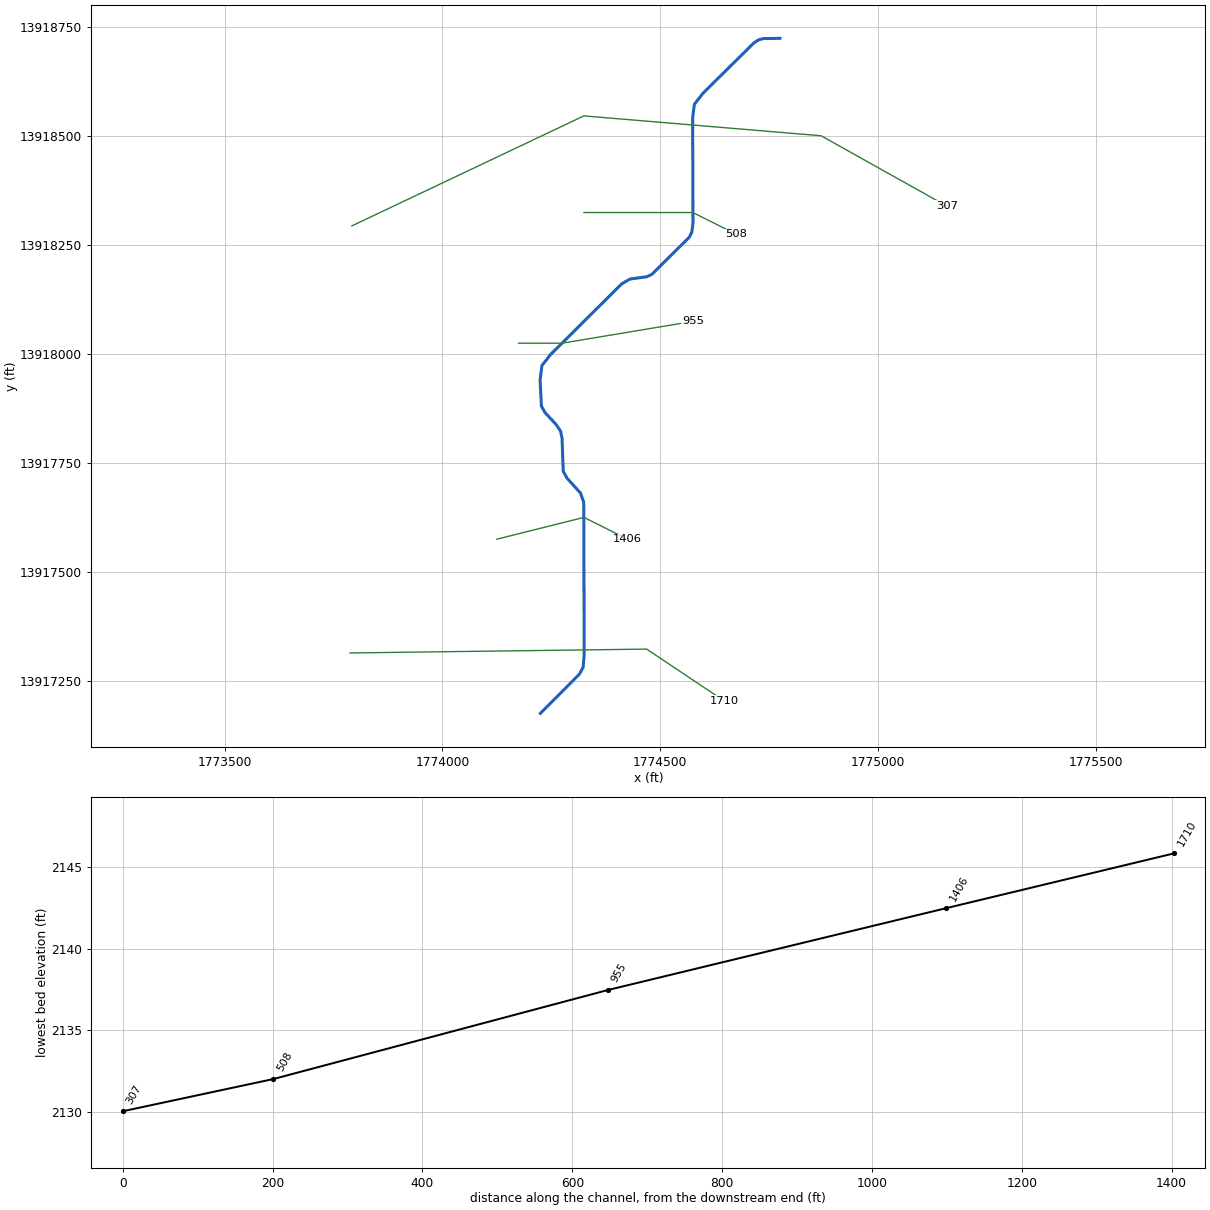
--- Stream1010.prj (project) ---

Proj Title=Stream1010 Base Level Engineering
Current Plan=p01
Default Exp/Contr=0.3,0.1
English Units
Geom File=g01
Flow File=f01
Plan File=p01
BEGIN DESCRIPTION:
Stream1010
END DESCRIPTION:

--- Stream1010.p01 (plan) ---

Plan Title=Multiple Run
Short Identifier=Multiple
Geom File=g01
Flow File=f01
Subcritical Flow
K Sum by GR= 0
Std Step Tol= 0.01
Critical Tol= 0.01
Num of Std Step Trials= 20
Max Error Tol= 0.3
Flow Tol Ratio= 0.001
Split Flow NTrial= 30
Split Flow Tol= 0.02
Split Flow Ratio= 0.02
Log Output Level= 0
Friction Slope Method= 1
Unsteady Friction Slope Method= 2
Unsteady Bridges Friction Slope Method= 1
Parabolic Critical Depth
Global Vel Dist=  1 , 1 , 1
Global Log Level= 0
CheckData=True
Encroach Param= -1, 0, 0, 0
BEGIN DESCRIPTION:
Multiple Run
END DESCRIPTION:

--- Stream1010.f01 (steady flow) ---

Flow Title=Multiple
Number of Profiles=7
Profile Names=10-year,25-year,50-year,1pct_min,100-year,1pct_plu,500-year
River Rch & RM= Stream1010,Reach-1,1710
    1001    1710    2385    1607    3206    6397    5731
Boundary for River Rch & Prof#=Stream1010,Reach-1,1
Up Type=0
Dn Type=3
Dn Slope=0.005
Boundary for River Rch & Prof#=Stream1010,Reach-1,2
Up Type=0
Dn Type=3
Dn Slope=0.005
Boundary for River Rch & Prof#=Stream1010,Reach-1,3
Up Type=0
Dn Type=3
Dn Slope=0.005
Boundary for River Rch & Prof#=Stream1010,Reach-1,4
Up Type=0
Dn Type=3
Dn Slope=0.005
Boundary for River Rch & Prof#=Stream1010,Reach-1,5
Up Type=0
Dn Type=3
Dn Slope=0.005
Boundary for River Rch & Prof#=Stream1010,Reach-1,6
Up Type=0
Dn Type=3
Dn Slope=0.005
Boundary for River Rch & Prof#=Stream1010,Reach-1,7
Up Type=0
Dn Type=3
Dn Slope=0.005

--- Stream1010.g01 (geometry) ---

Geom Title=Existing Conditions

River Reach=Stream1010,Reach-1
Reach XY= 30
      1774225.00     13917175.00      1774314.61     13917265.16
      1774322.98     13917280.84      1774325.49     13917309.80
      1774324.48     13917659.78      1774316.86     13917681.06
      1774285.89     13917715.37      1774277.36     13917730.98
      1774274.63     13917806.67      1774271.14     13917823.40
      1774261.17     13917838.13      1774235.81     13917865.37
      1774227.28     13917880.57      1774224.23     13917940.09
      1774228.46     13917973.50      1774247.84     13917998.52
      1774411.79     13918161.37      1774431.05     13918172.46
      1774468.96     13918177.53      1774481.07     13918183.15
      1774567.20     13918268.79      1774572.83     13918280.43
      1774575.37     13918302.12      1774574.54     13918543.37
      1774578.53     13918573.54      1774597.86     13918598.53
      1774715.21     13918714.49      1774726.35     13918721.73
      1774736.84     13918724.41      1774775.00     13918725.00

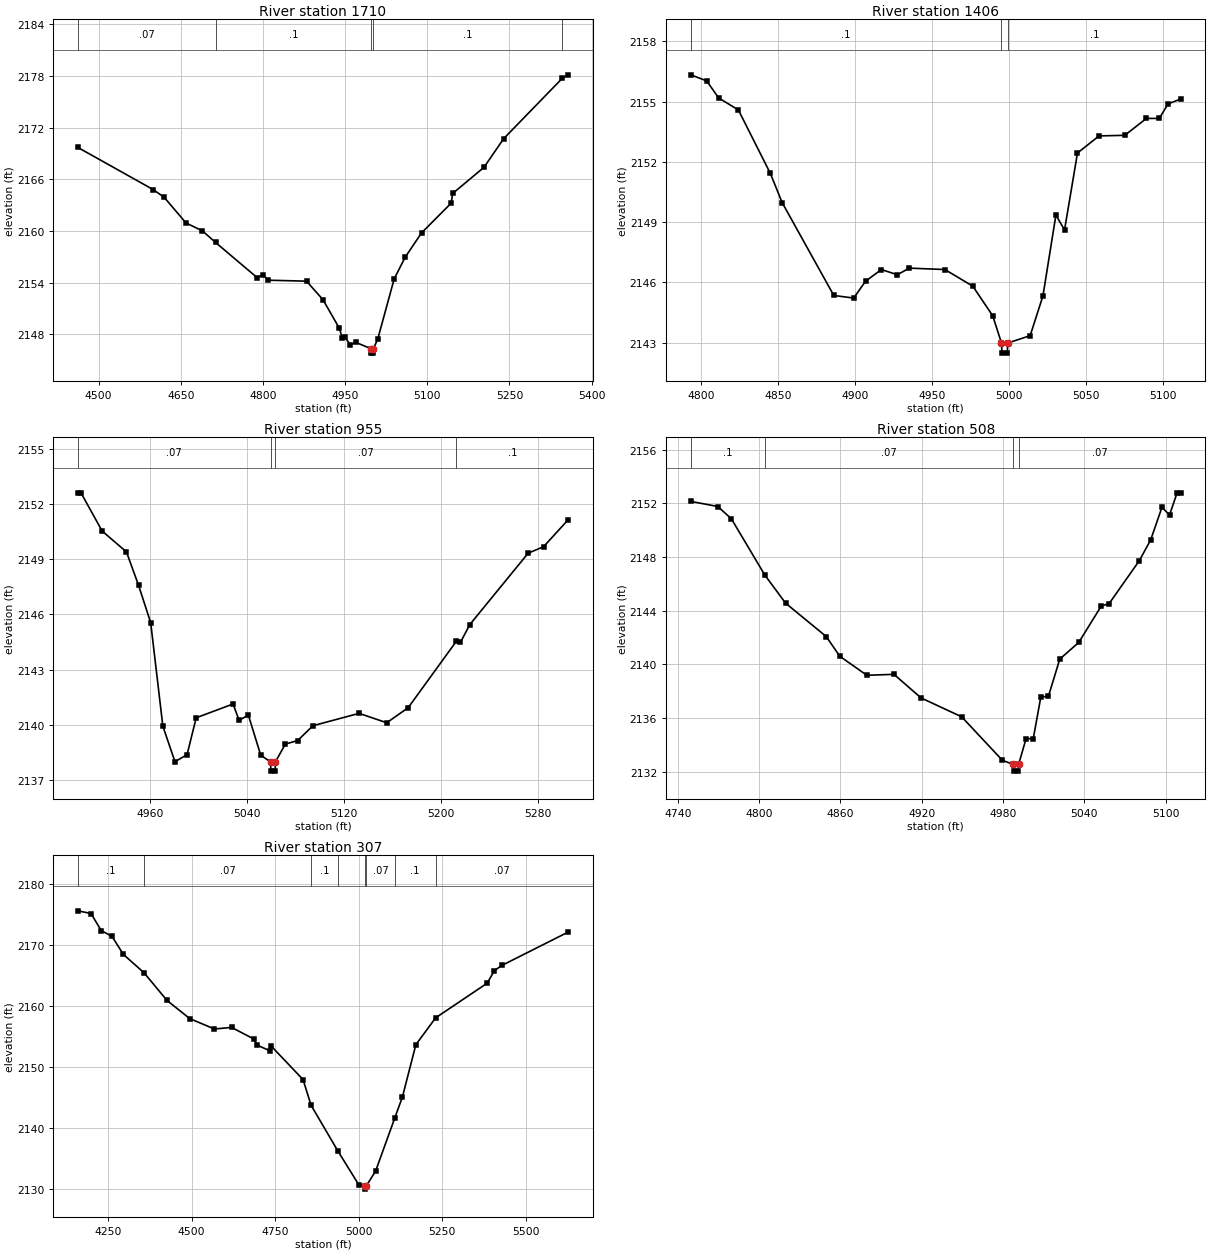
Type RM Length L Ch R = 1,1710,304,304,304
BEGIN DESCRIPTION:
Stream1010 4.0
END DESCRIPTION:
XS GIS Cut Line= 3
      1773787.67     13917313.73      1774469.01     13917322.58
      1774646.48     13917203.90
#Sta/Elev= 30
  4462.2 2169.69  4599.5 2164.81  4619.5 2163.92  4659.6 2160.93  4689.6 2160.01
  4713.5 2158.67  4789.6 2154.58  4799.6 2154.95  4809.6 2154.29  4879.6 2154.18
  4909.6 2152.03  4939.6 2148.70  4944.9 2147.58  4949.9 2147.67  4959.6 2146.79
  4969.6 2147.08  4997.6 2146.33  4997.8 2145.83  5001.3 2145.83  5001.6 2146.33
  5009.6 2147.46  5039.6 2154.44  5059.6 2156.95  5089.6 2159.78  5143.6 2163.23
  5146.5 2164.36  5203.6 2167.39  5239.6 2170.72  5346.3 2177.70  5357.1 2178.12
#Mann=5,-1,0
  4462.2    0.07       0  4713.5     0.1       0  4997.6    0.05       0
  5001.6     0.1       0  5346.3    0.07       0
Bank Sta=4997.6,5001.6
Exp/Cntr=0.3,0.1

Type RM Length L Ch R = 1,1406,451,451,451
BEGIN DESCRIPTION:
Stream1010 3.0
END DESCRIPTION:
XS GIS Cut Line= 3
      1774124.98     13917574.99      1774325.00     13917625.00
      1774425.02     13917574.99
#Sta/Elev= 30
  4793.4 2156.33  4803.7 2156.03  4811.5 2155.18  4824.3 2154.58  4845.0 2151.43
  4852.7 2149.97  4886.2 2145.35  4899.1 2145.22  4906.8 2146.06  4917.1 2146.64
  4927.4 2146.38  4935.2 2146.71  4958.3 2146.64  4976.4 2145.81  4989.3 2144.34
  4995.0 2142.98  4995.3 2142.48  4998.8 2142.48  4999.0 2142.98  5013.6 2143.35
  5021.9 2145.33  5030.3 2149.35  5035.9 2148.61  5044.3 2152.44  5058.3 2153.29
  5075.0 2153.32  5089.0 2154.16  5097.4 2154.16  5103.0 2154.88  5111.4 2155.13
#Mann=3,-1,0
  4793.4     0.1       0  4995.0    0.05       0  4999.0     0.1       0
Bank Sta=4995,4999
Exp/Cntr=0.3,0.1

Type RM Length L Ch R = 1,955,447,447,447
BEGIN DESCRIPTION:
Stream1010 2.0
END DESCRIPTION:
XS GIS Cut Line= 3
      1774175.01     13918025.00      1774275.00     13918025.00
      1774574.97     13918075.00
#Sta/Elev= 30
  4900.4 2152.61  4902.9 2152.61  4920.4 2150.53  4940.4 2149.40  4950.4 2147.58
  4960.4 2145.55  4970.4 2139.93  4980.4 2137.99  4990.4 2138.38  4997.9 2140.38
  5028.3 2141.13  5033.3 2140.24  5040.9 2140.53  5051.1 2138.35  5059.2 2137.98
  5059.5 2137.48  5063.0 2137.48  5063.2 2137.98  5071.4 2138.95  5081.5 2139.14
  5094.2 2139.95  5132.2 2140.62  5155.0 2140.11  5172.7 2140.93  5212.5 2144.55
  5215.8 2144.48  5223.4 2145.44  5271.6 2149.33  5284.3 2149.68  5304.5 2151.14
#Mann=4,-1,0
  4900.4    0.07       0  5059.2    0.05       0  5063.2    0.07       0
  5212.5     0.1       0
Bank Sta=5059.2,5063.2
Exp/Cntr=0.3,0.1

Type RM Length L Ch R = 1,508,201,201,201
BEGIN DESCRIPTION:
Stream1010 1.0
END DESCRIPTION:
XS GIS Cut Line= 3
      1774324.98     13918325.00      1774575.00     13918325.00
      1774674.98     13918275.01
#Sta/Elev= 30
  4749.5 2152.15  4769.5 2151.77  4779.5 2150.85  4804.2 2146.65  4819.5 2144.56
  4849.5 2142.07  4859.5 2140.60  4879.5 2139.18  4899.5 2139.25  4919.5 2137.49
  4949.5 2136.08  4979.5 2132.84  4987.5 2132.53  4987.8 2132.03  4991.3 2132.03
  4991.5 2132.53  4997.0 2134.45  5002.3 2134.45  5007.9 2137.56  5013.5 2137.61
  5021.9 2140.39  5035.9 2141.63  5052.6 2144.36  5058.2 2144.51  5080.6 2147.73
  5089.0 2149.28  5097.3 2151.71  5102.9 2151.14  5108.5 2152.79  5111.3 2152.79
#Mann=4,-1,0
  4749.5     0.1       0  4804.2    0.07       0  4987.5    0.05       0
  4991.5    0.07       0
Bank Sta=4987.5,4991.5
Exp/Cntr=0.3,0.1

Type RM Length L Ch R = 1,307,0,0,0
BEGIN DESCRIPTION:
Stream1010 0.0
END DESCRIPTION:
XS GIS Cut Line= 4
      1773792.06     13918294.37      1774324.78     13918546.92
      1774869.45     13918501.29      1775157.97     13918339.94
#Sta/Elev= 30
  4159.8 2175.67  4199.0 2175.23  4229.5 2172.44  4261.7 2171.49  4295.9 2168.52
  4357.6 2165.52  4426.4 2160.98  4494.6 2158.00  4568.4 2156.30  4619.4 2156.57
  4687.6 2154.62  4694.3 2153.70  4733.1 2152.76  4738.6 2153.48  4833.5 2148.01
  4857.5 2143.80  4938.2 2136.26  5000.4 2130.76  5018.5 2130.56  5018.8 2130.06
  5022.5 2130.56  5050.6 2133.02  5108.1 2141.74  5130.9 2145.18  5171.0 2153.73
  5230.1 2158.13  5384.4 2163.81  5406.1 2165.87  5428.3 2166.72  5626.5 2172.18
#Mann=8,-1,0
  4159.8     0.1       0  4357.6    0.07       0  4857.5     0.1       0
  4938.2    0.07       0  5018.5    0.05       0  5022.5    0.07       0
  5108.1     0.1       0  5230.1    0.07       0
Bank Sta=5018.5,5022.5
Exp/Cntr=0.3,0.1

Chan Stop Cuts=-1