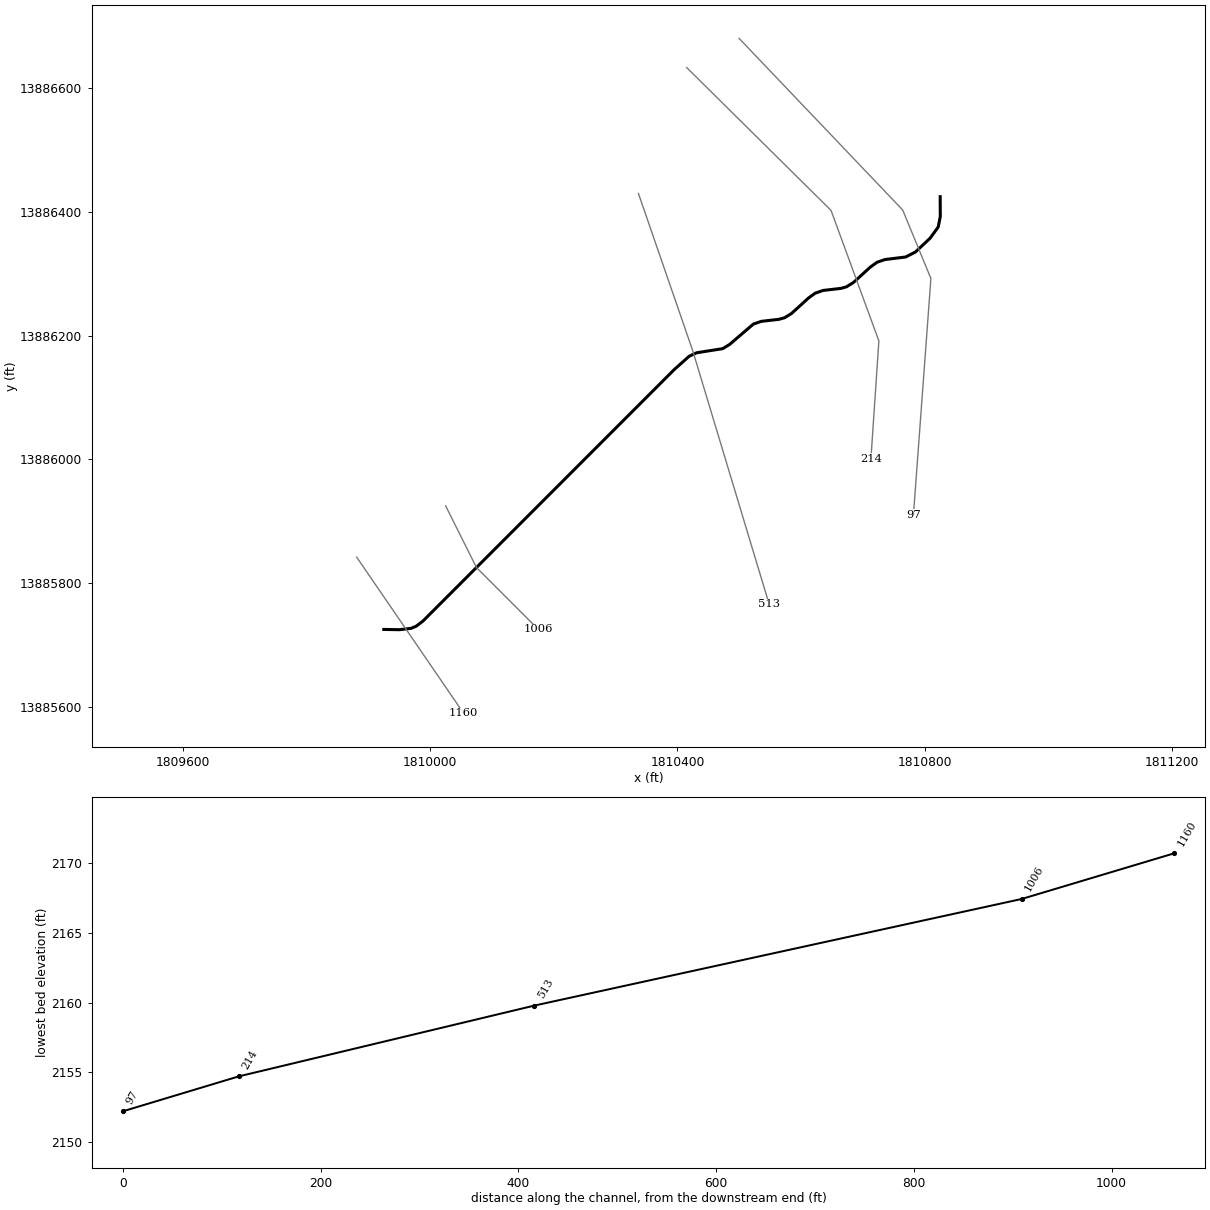
--- Stream1012.prj (project) ---

Proj Title=Stream1012 Base Level Engineering
Current Plan=p01
Default Exp/Contr=0.3,0.1
English Units
Geom File=g01
Flow File=f01
Plan File=p01
BEGIN DESCRIPTION:
Stream1012
END DESCRIPTION:

--- Stream1012.p01 (plan) ---

Plan Title=Multiple Run
Short Identifier=Multiple
Geom File=g01
Flow File=f01
Subcritical Flow
K Sum by GR= 0
Std Step Tol= 0.01
Critical Tol= 0.01
Num of Std Step Trials= 20
Max Error Tol= 0.3
Flow Tol Ratio= 0.001
Split Flow NTrial= 30
Split Flow Tol= 0.02
Split Flow Ratio= 0.02
Log Output Level= 0
Friction Slope Method= 1
Unsteady Friction Slope Method= 2
Unsteady Bridges Friction Slope Method= 1
Parabolic Critical Depth
Global Vel Dist=  1 , 1 , 1
Global Log Level= 0
CheckData=True
Encroach Param= -1, 0, 0, 0
BEGIN DESCRIPTION:
Multiple Run
END DESCRIPTION:

--- Stream1012.f01 (steady flow) ---

Flow Title=Multiple
Number of Profiles=7
Profile Names=10-year,25-year,50-year,1pct_min,100-year,1pct_plu,500-year
River Rch & RM= Stream1012,Reach-1,1160
     539     885    1201     791    1578    3149    2687
Boundary for River Rch & Prof#=Stream1012,Reach-1,1
Up Type=0
Dn Type=3
Dn Slope=0.005
Boundary for River Rch & Prof#=Stream1012,Reach-1,2
Up Type=0
Dn Type=3
Dn Slope=0.005
Boundary for River Rch & Prof#=Stream1012,Reach-1,3
Up Type=0
Dn Type=3
Dn Slope=0.005
Boundary for River Rch & Prof#=Stream1012,Reach-1,4
Up Type=0
Dn Type=3
Dn Slope=0.005
Boundary for River Rch & Prof#=Stream1012,Reach-1,5
Up Type=0
Dn Type=3
Dn Slope=0.005
Boundary for River Rch & Prof#=Stream1012,Reach-1,6
Up Type=0
Dn Type=3
Dn Slope=0.005
Boundary for River Rch & Prof#=Stream1012,Reach-1,7
Up Type=0
Dn Type=3
Dn Slope=0.005

--- Stream1012.g01 (geometry) ---

Geom Title=Existing Conditions

River Reach=Stream1012,Reach-1
Reach XY= 30
      1809925.00     13885725.00      1809950.37     13885724.59
      1809968.86     13885726.68      1809977.52     13885730.31
      1809988.27     13885738.47      1810394.84     13886145.39
      1810418.94     13886166.86      1810431.03     13886172.50
      1810473.26     13886179.19      1810484.54     13886186.10
      1810522.80     13886218.92      1810535.69     13886223.35
      1810564.31     13886226.65      1810573.28     13886229.16
      1810584.55     13886236.08      1810611.93     13886261.03
      1810622.80     13886268.92      1810635.69     13886273.35
      1810664.32     13886276.65      1810673.28     13886279.16
      1810684.55     13886286.08      1810711.94     13886311.02
      1810722.82     13886318.91      1810735.72     13886323.32
      1810769.11     13886327.42      1810784.98     13886335.55
      1810808.64     13886357.76      1810821.86     13886376.03
      1810825.15     13886392.95      1810825.00     13886425.00

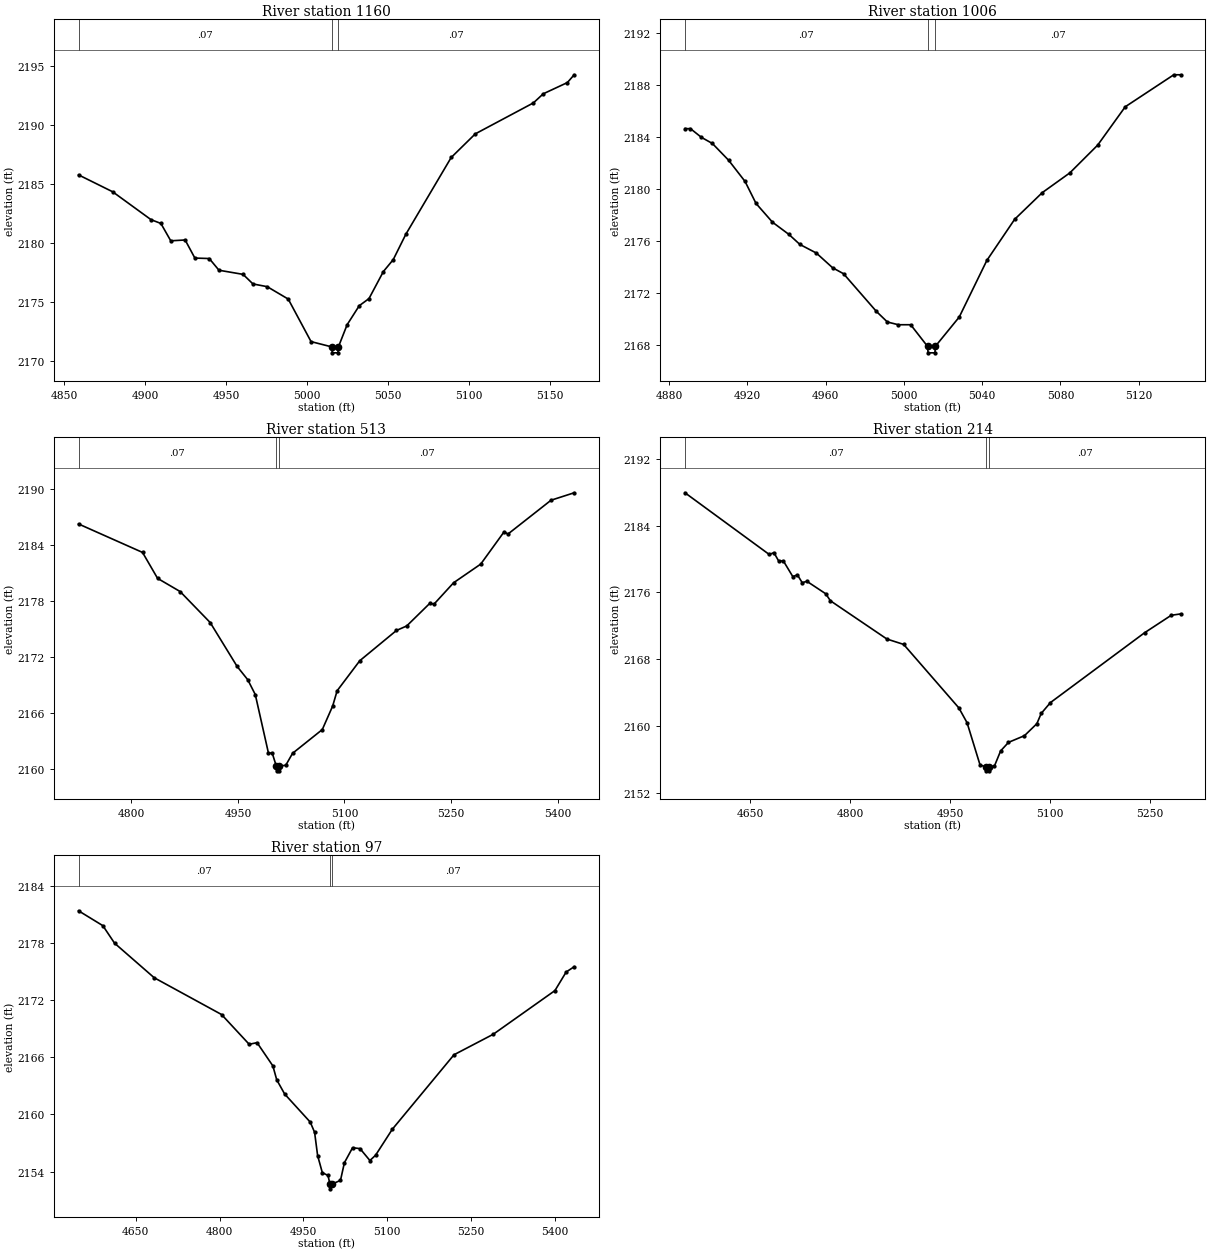
Type RM Length L Ch R = 1,1160,154,154,154
BEGIN DESCRIPTION:
Stream1012 3.0
END DESCRIPTION:
XS GIS Cut Line= 2
      1809881.15     13885841.94      1810054.23     13885589.23
#Sta/Elev= 30
  4858.7 2185.76  4879.8 2184.33  4903.5 2181.97  4909.6 2181.65  4915.7 2180.18
  4924.6 2180.25  4930.6 2178.72  4939.5 2178.68  4945.5 2177.69  4960.4 2177.34
  4966.5 2176.53  4975.3 2176.30  4988.3 2175.25  5002.4 2171.65  5015.3 2171.20
  5015.5 2170.70  5019.0 2170.70  5019.3 2171.20  5024.7 2173.08  5032.2 2174.69
  5038.2 2175.29  5047.1 2177.58  5053.2 2178.59  5061.0 2180.74  5089.0 2187.23
  5103.9 2189.23  5139.8 2191.85  5145.9 2192.62  5160.8 2193.57  5165.0 2194.23
#Mann=3,-1,0
  4858.7    0.07       0  5015.3    0.05       0  5019.3    0.07       0
Bank Sta=5015.3,5019.3
Exp/Cntr=0.3,0.1

Type RM Length L Ch R = 1,1006,493,493,493
BEGIN DESCRIPTION:
Stream1012 2.0
END DESCRIPTION:
XS GIS Cut Line= 3
      1810025.01     13885924.98      1810075.00     13885825.00
      1810175.00     13885725.00
#Sta/Elev= 30
  4888.2 2184.66  4891.0 2184.66  4896.6 2183.99  4902.2 2183.52  4910.5 2182.23
  4918.9 2180.60  4924.5 2178.91  4932.9 2177.47  4941.3 2176.53  4946.9 2175.76
  4955.3 2175.10  4963.6 2173.97  4969.2 2173.51  4986.0 2170.61  4991.6 2169.80
  4997.2 2169.59  5003.5 2169.59  5012.1 2167.93  5012.4 2167.43  5015.9 2167.43
  5016.1 2167.93  5028.3 2170.18  5042.4 2174.53  5056.6 2177.69  5070.7 2179.74
  5084.8 2181.26  5099.0 2183.39  5113.1 2186.34  5137.9 2188.80  5141.4 2188.80
#Mann=3,-1,0
  4888.2    0.07       0  5012.1    0.05       0  5016.1    0.07       0
Bank Sta=5012.1,5016.1
Exp/Cntr=0.3,0.1

Type RM Length L Ch R = 1,513,299,299,299
BEGIN DESCRIPTION:
Stream1012 1.0
END DESCRIPTION:
XS GIS Cut Line= 3
      1810336.89     13886430.20      1810425.00     13886175.00
      1810548.42     13885765.58
#Sta/Elev= 30
  4725.7 2186.23  4815.8 2183.18  4837.0 2180.40  4868.7 2178.99  4911.0 2175.67
  4948.9 2170.97  4963.9 2169.54  4974.5 2167.95  4993.0 2161.69  4998.3 2161.69
  5004.1 2160.28  5004.4 2159.78  5007.9 2159.78  5008.1 2160.28  5017.4 2160.38
  5027.0 2161.66  5068.8 2164.20  5083.4 2166.72  5089.7 2168.36  5121.6 2171.58
  5173.2 2174.82  5187.6 2175.30  5220.6 2177.76  5225.8 2177.62  5253.6 2179.93
  5291.8 2181.93  5324.8 2185.40  5330.0 2185.14  5390.7 2188.77  5423.3 2189.57
#Mann=3,-1,0
  4725.7    0.07       0  5004.1    0.05       0  5008.1    0.07       0
Bank Sta=5004.1,5008.1
Exp/Cntr=0.3,0.1

Type RM Length L Ch R = 1,214,117,117,117
BEGIN DESCRIPTION:
Stream1012 0.0
END DESCRIPTION:
XS GIS Cut Line= 4
      1810414.91     13886633.90      1810648.44     13886402.81
      1810725.82     13886191.71      1810712.95     13886000.92
#Sta/Elev= 30
  4551.7 2187.91  4678.3 2180.54  4685.3 2180.76  4692.4 2179.77  4699.5 2179.77
  4713.6 2177.91  4720.7 2178.10  4727.8 2177.17  4734.8 2177.34  4763.1 2175.85
  4770.2 2175.01  4855.1 2170.44  4880.2 2169.80  4963.1 2162.22  4975.5 2160.44
  4995.1 2155.37  5004.0 2155.20  5004.3 2154.70  5007.8 2154.70  5008.0 2155.20
  5016.4 2155.24  5025.9 2157.08  5037.7 2158.10  5061.7 2158.90  5080.3 2160.33
  5086.9 2161.56  5100.7 2162.85  5242.1 2171.19  5282.2 2173.28  5296.3 2173.44
#Mann=3,-1,0
  4551.7    0.07       0  5004.0    0.05       0  5008.0    0.07       0
Bank Sta=5004,5008
Exp/Cntr=0.3,0.1

Type RM Length L Ch R = 1,97,0,0,0
BEGIN DESCRIPTION:
Stream1012 0.1
END DESCRIPTION:
XS GIS Cut Line= 4
      1810499.66     13886681.12      1810764.40     13886403.36
      1810809.97     13886292.68      1810781.76     13885910.73
#Sta/Elev= 30
  4547.8 2181.36  4591.3 2179.80  4612.3 2177.96  4683.1 2174.34  4803.6 2170.48
  4853.0 2167.36  4867.1 2167.53  4895.4 2165.09  4902.3 2163.63  4916.5 2162.14
  4962.2 2159.20  4970.0 2158.13  4975.4 2155.69  4983.8 2153.90  4994.0 2153.60
  4997.4 2152.70  4997.6 2152.20  5001.4 2152.70  5016.3 2153.09  5023.3 2154.94
  5037.9 2156.51  5051.2 2156.42  5068.9 2155.17  5079.0 2155.72  5109.0 2158.45
  5219.3 2166.26  5289.5 2168.41  5399.8 2172.99  5419.9 2174.94  5434.2 2175.49
#Mann=3,-1,0
  4547.8    0.07       0  4997.4    0.05       0  5001.4    0.07       0
Bank Sta=4997.4,5001.4
Exp/Cntr=0.3,0.1

Chan Stop Cuts=-1