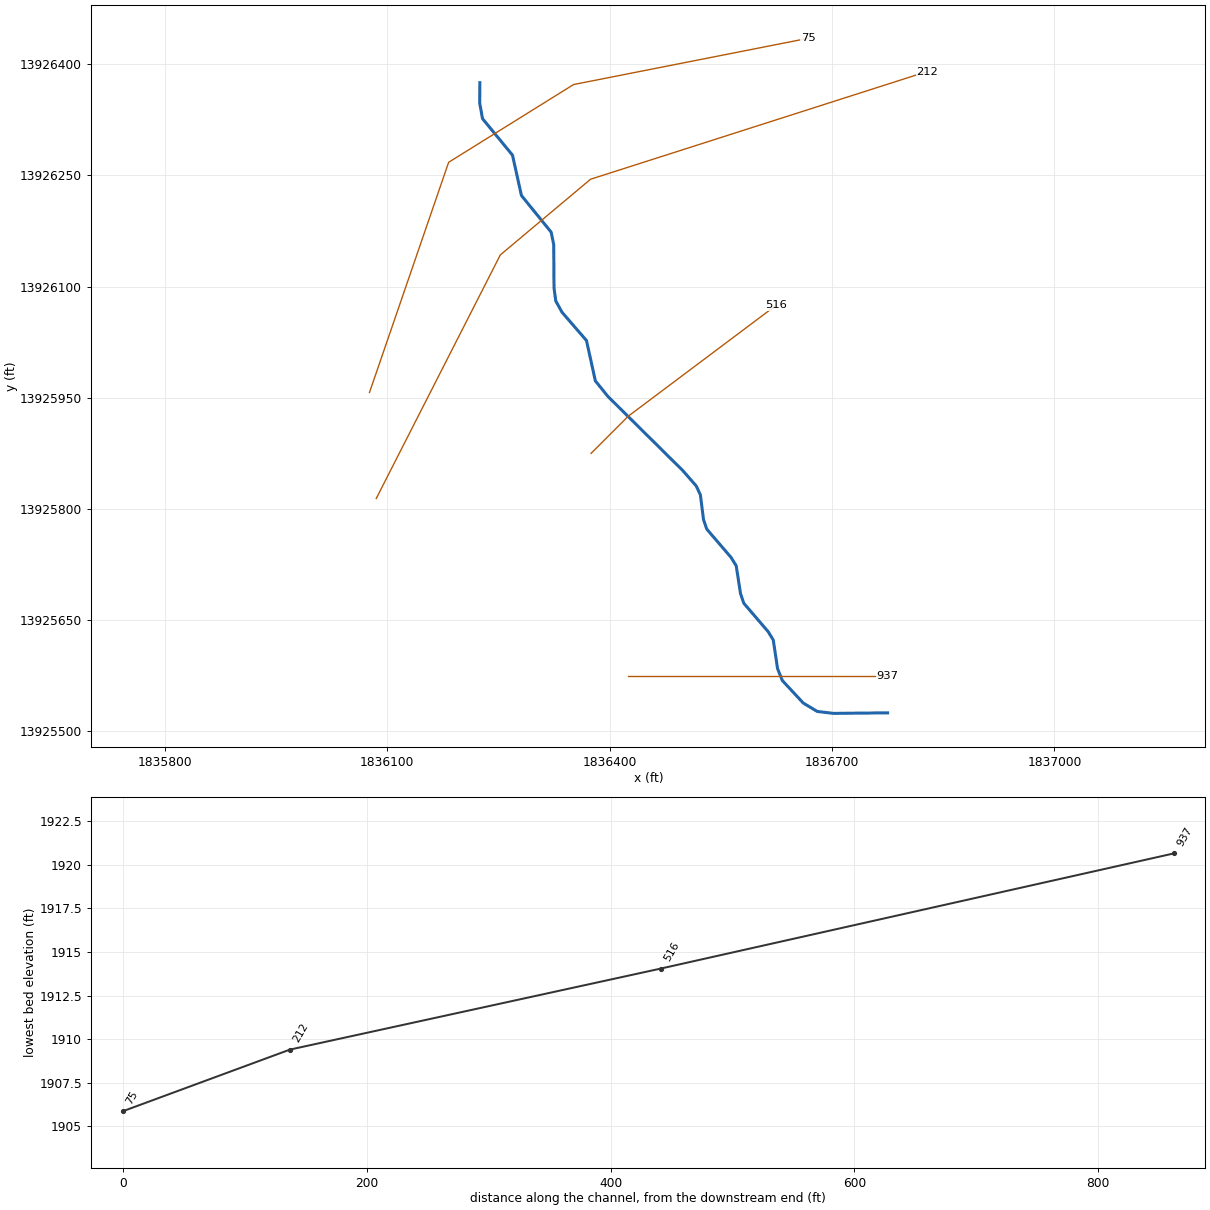
--- Stream1014.prj (project) ---

Proj Title=Stream1014 Base Level Engineering
Current Plan=p01
Default Exp/Contr=0.3,0.1
English Units
Geom File=g01
Flow File=f01
Plan File=p01
Y Axis Title=Elevation
X Axis Title(PF)=Main Channel Distance
X Axis Title(XS)=Station
BEGIN DESCRIPTION:
Stream1014
END DESCRIPTION:
DSS Export Rating Curves= 0
DSS Export Rating Curve Sorted= 0
DSS Export Volume Flow Curves= 0
DXF OffsetX= 0
DXF OffsetY= 0
DXF ScaleX= 1
DXF ScaleY= 10

--- Stream1014.p01 (plan) ---

Plan Title=Multiple Run
Short Identifier=Multiple
Geom File=g01
Flow File=f01
Subcritical Flow
K Sum by GR= 0
Std Step Tol= 0.01
Critical Tol= 0.01
Num of Std Step Trials= 20
Max Error Tol= 0.3
Flow Tol Ratio= 0.001
Split Flow NTrial= 30
Split Flow Tol= 0.02
Split Flow Ratio= 0.02
Log Output Level= 0
Friction Slope Method= 1
Unsteady Friction Slope Method= 2
Unsteady Bridges Friction Slope Method= 1
Parabolic Critical Depth
Global Vel Dist=  1 , 1 , 1
Global Log Level= 0
CheckData=True
Encroach Param= -1, 0, 0, 0
BEGIN DESCRIPTION:
Multiple Run
END DESCRIPTION:

--- Stream1014.f01 (steady flow) ---

Flow Title=Multiple
Program Version=4.10
Number of Profiles= 7
Profile Names=10-year,25-year,50-year,1pct_min,100-year,1pct_plu,500-year
River Rch & RM=Stream1014,Reach-1         ,937
    1392    2451    3492    2407    4803    9582    8974
Boundary for River Rch & Prof#=Stream1014,Reach-1         , 1
Up Type= 0
Dn Type= 3
Dn Slope=0.017
Boundary for River Rch & Prof#=Stream1014,Reach-1         , 2
Up Type= 0
Dn Type= 3
Dn Slope=0.017
Boundary for River Rch & Prof#=Stream1014,Reach-1         , 3
Up Type= 0
Dn Type= 3
Dn Slope=0.017
Boundary for River Rch & Prof#=Stream1014,Reach-1         , 4
Up Type= 0
Dn Type= 3
Dn Slope=0.017
Boundary for River Rch & Prof#=Stream1014,Reach-1         , 5
Up Type= 0
Dn Type= 3
Dn Slope=0.017
Boundary for River Rch & Prof#=Stream1014,Reach-1         , 6
Up Type= 0
Dn Type= 3
Dn Slope=0.017
Boundary for River Rch & Prof#=Stream1014,Reach-1         , 7
Up Type= 0
Dn Type= 3
Dn Slope=0.017
DSS Import GetInterval= 0
DSS Import GetPeak= 0
DSS Import FillOption= 0

--- Stream1014.g01 (geometry) ---

Geom Title=Existing Conditions

River Reach=Stream1014,Reach-1
Reach XY= 30
      1836775.00     13925525.00      1836701.89     13925524.29
      1836680.14     13925526.88      1836661.28     13925538.19
      1836632.99     13925568.62      1836626.58     13925584.61
      1836620.80     13925623.24      1836613.89     13925634.53
      1836581.08     13925672.80      1836576.65     13925685.68
      1836570.84     13925723.28      1836563.92     13925734.55
      1836531.10     13925772.81      1836526.70     13925785.70
      1836522.50     13925818.96      1836516.86     13925831.06
      1836498.71     13925851.82      1836398.01     13925951.53
      1836380.83     13925972.70      1836368.86     13926027.17
      1836335.84     13926065.35      1836327.44     13926080.56
      1836325.08     13926097.76      1836324.64     13926156.67
      1836321.18     13926173.42      1836281.10     13926222.81
      1836269.05     13926277.25      1836228.60     13926326.49
      1836224.82     13926347.32      1836225.00     13926375.00

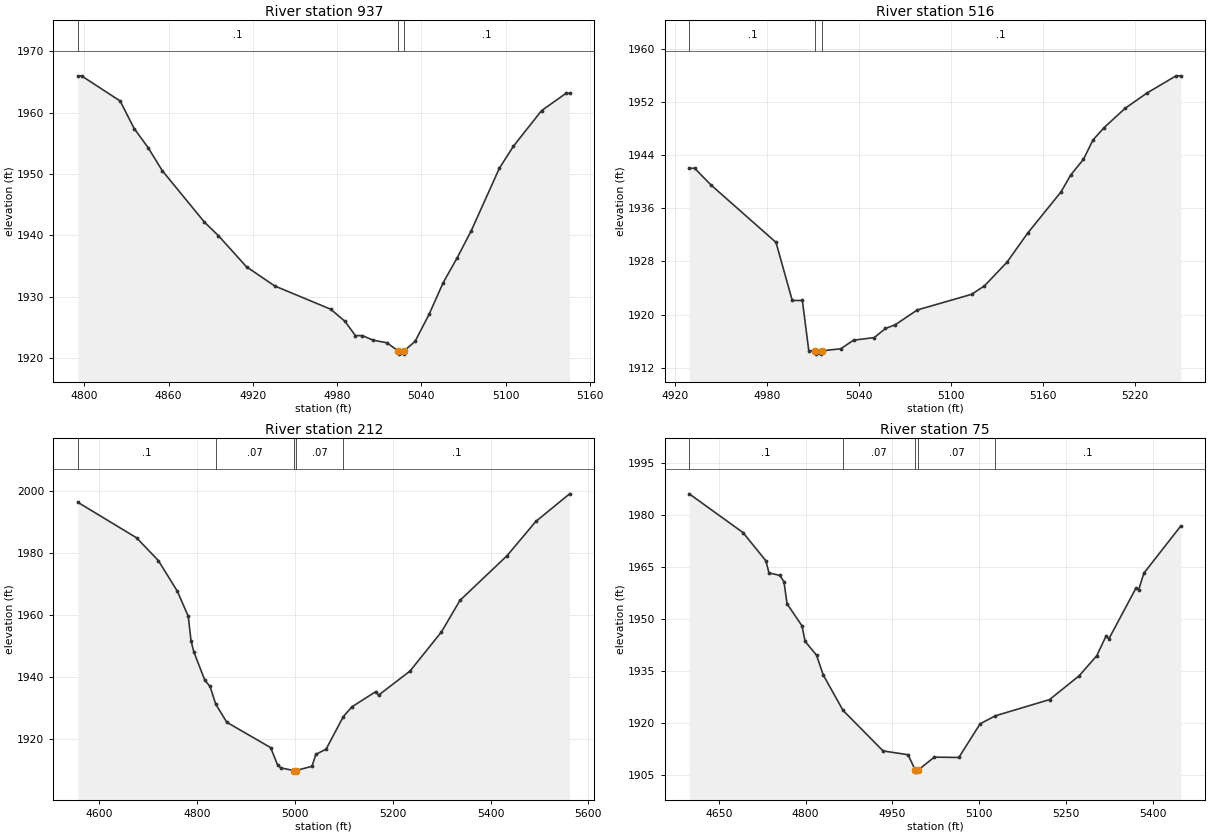
Type RM Length L Ch R = 1,937,421,421,421
BEGIN DESCRIPTION:
Stream1014 2.0
END DESCRIPTION:
XS GIS Cut Line= 3
      1836424.99     13925575.00      1836625.00     13925575.00
      1836774.99     13925575.00
#Sta/Elev= 30
  4795.5 1966.00  4798.0 1966.00  4825.5 1961.90  4835.5 1957.41  4845.5 1954.27
  4855.5 1950.54  4885.5 1942.16  4895.5 1939.94  4915.5 1934.87  4935.5 1931.76
  4975.5 1927.95  4985.5 1926.00  4993.0 1923.66  4998.0 1923.66  5005.5 1922.92
  5015.5 1922.49  5023.5 1921.14  5023.8 1920.64  5027.3 1920.64  5027.5 1921.14
  5035.5 1922.72  5045.5 1927.15  5055.5 1932.29  5065.5 1936.36  5075.5 1940.76
  5095.5 1950.94  5105.5 1954.53  5125.5 1960.32  5143.0 1963.16  5145.5 1963.16
#Mann=3,-1,0
  4795.5     0.1       0  5023.5    0.05       0  5027.5     0.1       0
Bank Sta=5023.5,5027.5
Exp/Cntr=0.3,0.1

Type RM Length L Ch R = 1,516,304,304,304
BEGIN DESCRIPTION:
Stream1014 1.0
END DESCRIPTION:
XS GIS Cut Line= 3
      1836374.99     13925874.99      1836425.00     13925925.00
      1836624.98     13926074.99
#Sta/Elev= 30
  4929.5 1942.02  4933.0 1942.02  4943.7 1939.50  4986.1 1930.86  4996.7 1922.12
  5003.3 1922.12  5007.5 1914.55  5011.8 1914.54  5012.0 1914.04  5015.5 1914.04
  5015.8 1914.54  5028.3 1914.84  5036.7 1916.14  5050.2 1916.53  5057.5 1917.90
  5063.8 1918.45  5078.3 1920.69  5113.8 1923.05  5122.1 1924.32  5136.7 1927.85
  5150.2 1932.23  5172.1 1938.48  5178.3 1940.99  5186.7 1943.38  5192.9 1946.28
  5200.2 1948.15  5213.8 1951.03  5228.3 1953.37  5247.1 1955.93  5250.2 1955.93
#Mann=3,-1,0
  4929.5     0.1       0  5011.8    0.05       0  5015.8     0.1       0
Bank Sta=5011.8,5015.8
Exp/Cntr=0.3,0.1

Type RM Length L Ch R = 1,212,137,137,137
BEGIN DESCRIPTION:
Stream1014 0.0
END DESCRIPTION:
XS GIS Cut Line= 4
      1836085.25     13925814.11      1836252.63     13926142.70
      1836374.34     13926244.77      1836828.45     13926390.07
#Sta/Elev= 30
  4557.2 1996.28  4676.9 1984.87  4721.4 1977.54  4760.2 1967.67  4782.5 1959.58
  4788.1 1951.74  4793.9 1948.10  4816.3 1939.01  4827.0 1936.99  4838.6 1931.32
  4861.2 1925.46  4950.8 1917.30  4965.1 1911.68  4971.6 1910.77  4998.2 1909.90
  4998.5 1909.40  5002.2 1909.90  5035.3 1911.28  5043.1 1915.13  5064.0 1916.78
  5099.3 1927.30  5117.0 1930.45  5165.9 1935.36  5171.2 1934.18  5235.5 1941.95
  5299.8 1954.57  5337.5 1964.70  5433.7 1979.10  5492.7 1990.16  5561.6 1999.04
#Mann=5,-1,0
  4557.2     0.1       0  4838.6    0.07       0  4998.2    0.05       0
  5002.2    0.07       0  5099.3     0.1       0
Bank Sta=4998.2,5002.2
Exp/Cntr=0.3,0.1

Type RM Length L Ch R = 1,75,0,0,0
BEGIN DESCRIPTION:
Stream1014 0.1
END DESCRIPTION:
XS GIS Cut Line= 4
      1836076.15     13925957.16      1836182.90     13926267.60
      1836351.42     13926372.50      1836667.55     13926434.83
#Sta/Elev= 30
  4599.1 1986.01  4692.0 1974.85  4731.5 1966.72  4736.8 1963.26  4755.4 1962.51
  4762.7 1960.74  4768.0 1954.37  4793.9 1947.97  4799.2 1943.53  4818.9 1939.56
  4830.5 1933.87  4864.7 1923.66  4933.8 1911.98  4977.0 1910.88  4989.7 1906.37
  4989.9 1905.87  4993.7 1906.37  5022.4 1910.19  5064.8 1910.09  5101.4 1919.78
  5127.8 1922.09  5221.4 1926.76  5272.7 1933.64  5302.8 1939.37  5318.9 1945.04
  5324.0 1944.30  5370.3 1958.77  5375.3 1958.42  5384.3 1963.17  5448.1 1976.77
#Mann=5,-1,0
  4599.1     0.1       0  4864.7    0.07       0  4989.7    0.05       0
  4993.7    0.07       0  5127.8     0.1       0
Bank Sta=4989.7,4993.7
Exp/Cntr=0.3,0.1

Chan Stop Cuts=-1