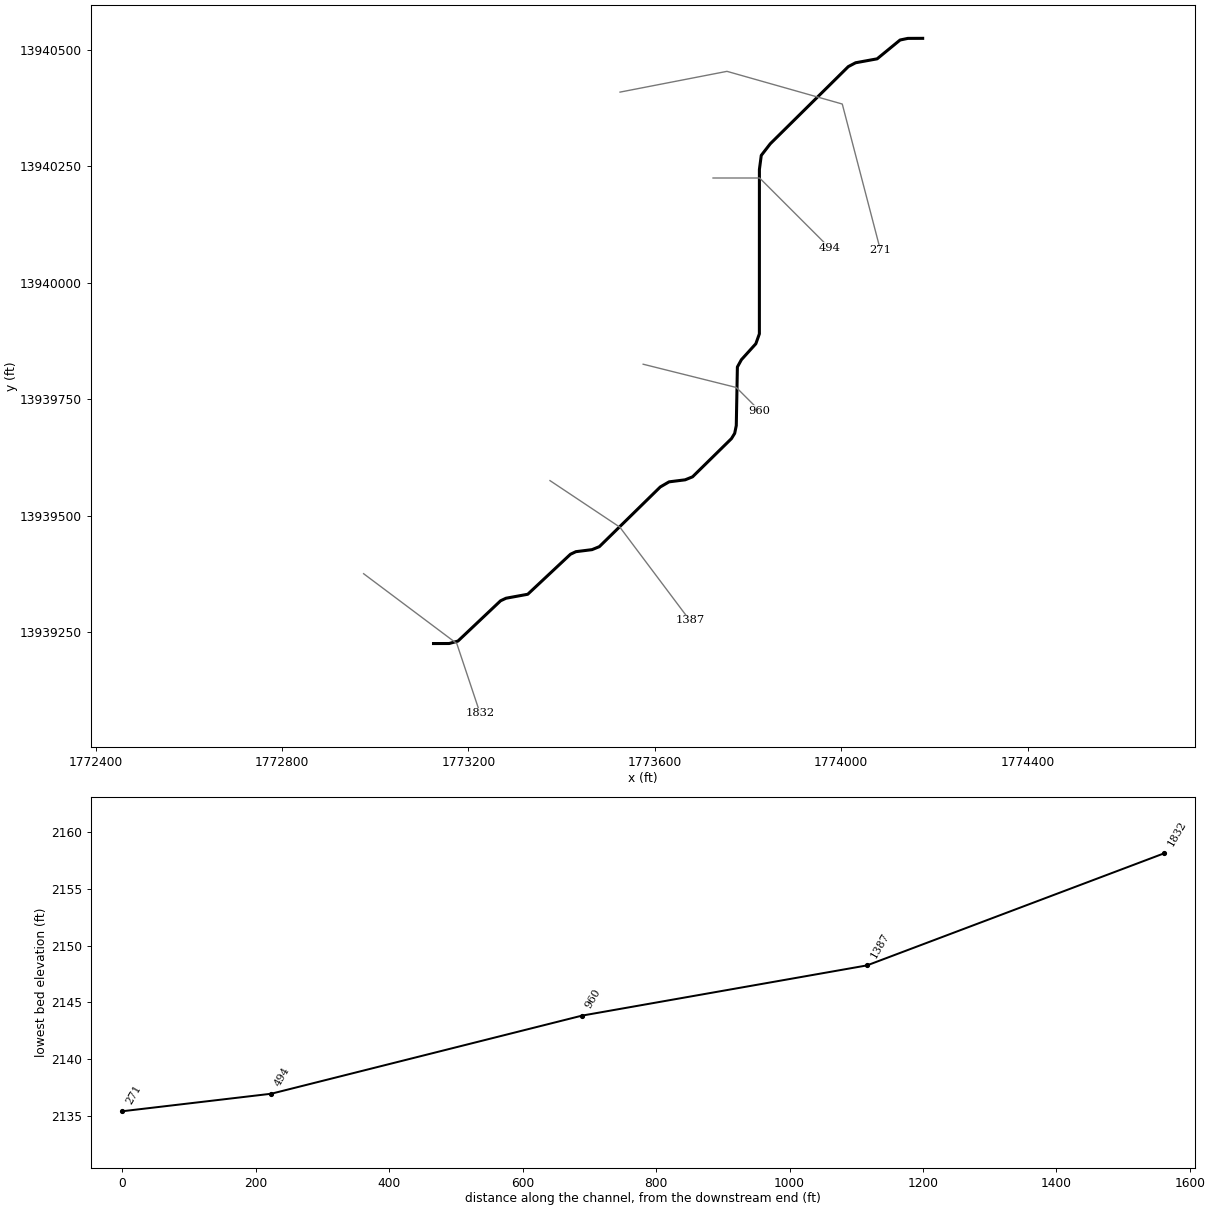
--- Stream1015.prj (project) ---

Proj Title=Stream1015 Base Level Engineering
Current Plan=p01
Default Exp/Contr=0.3,0.1
English Units
Geom File=g01
Flow File=f01
Plan File=p01
BEGIN DESCRIPTION:
Stream1015
END DESCRIPTION:

--- Stream1015.p01 (plan) ---

Plan Title=Multiple Run
Short Identifier=Multiple
Geom File=g01
Flow File=f01
Subcritical Flow
K Sum by GR= 0
Std Step Tol= 0.01
Critical Tol= 0.01
Num of Std Step Trials= 20
Max Error Tol= 0.3
Flow Tol Ratio= 0.001
Split Flow NTrial= 30
Split Flow Tol= 0.02
Split Flow Ratio= 0.02
Log Output Level= 0
Friction Slope Method= 1
Unsteady Friction Slope Method= 2
Unsteady Bridges Friction Slope Method= 1
Parabolic Critical Depth
Global Vel Dist=  1 , 1 , 1
Global Log Level= 0
CheckData=True
Encroach Param= -1, 0, 0, 0
BEGIN DESCRIPTION:
Multiple Run
END DESCRIPTION:

--- Stream1015.f01 (steady flow) ---

Flow Title=Multiple
Number of Profiles=7
Profile Names=10-year,25-year,50-year,1pct_min,100-year,1pct_plu,500-year
River Rch & RM= Stream1015,Reach-1,1832
     799    1345    1857    1240    2474    4936    4338
Boundary for River Rch & Prof#=Stream1015,Reach-1,1
Up Type=0
Dn Type=3
Dn Slope=0.005
Boundary for River Rch & Prof#=Stream1015,Reach-1,2
Up Type=0
Dn Type=3
Dn Slope=0.005
Boundary for River Rch & Prof#=Stream1015,Reach-1,3
Up Type=0
Dn Type=3
Dn Slope=0.005
Boundary for River Rch & Prof#=Stream1015,Reach-1,4
Up Type=0
Dn Type=3
Dn Slope=0.005
Boundary for River Rch & Prof#=Stream1015,Reach-1,5
Up Type=0
Dn Type=3
Dn Slope=0.005
Boundary for River Rch & Prof#=Stream1015,Reach-1,6
Up Type=0
Dn Type=3
Dn Slope=0.005
Boundary for River Rch & Prof#=Stream1015,Reach-1,7
Up Type=0
Dn Type=3
Dn Slope=0.005

--- Stream1015.g01 (geometry) ---

Geom Title=Existing Conditions

River Reach=Stream1015,Reach-1
Reach XY= 30
      1773125.00     13939225.00      1773158.63     13939225.08
      1773177.51     13939230.33      1773268.95     13939316.84
      1773280.64     13939322.35      1773327.28     13939330.87
      1773418.96     13939416.82      1773430.64     13939422.35
      1773465.21     13939426.70      1773481.05     13939433.16
      1773611.79     13939561.37      1773630.64     13939572.35
      1773665.21     13939576.70      1773681.07     13939583.15
      1773764.53     13939665.18      1773771.46     13939676.46
      1773774.90     13939693.22      1773777.27     13939819.06
      1773785.86     13939834.64      1773816.86     13939868.94
      1773824.48     13939890.22      1773824.54     13940243.37
      1773828.54     13940273.54      1773847.86     13940298.53
      1774015.31     13940464.25      1774031.02     13940472.53
      1774077.24     13940480.97      1774126.49     13940521.40
      1774143.19     13940524.90      1774175.00     13940525.00

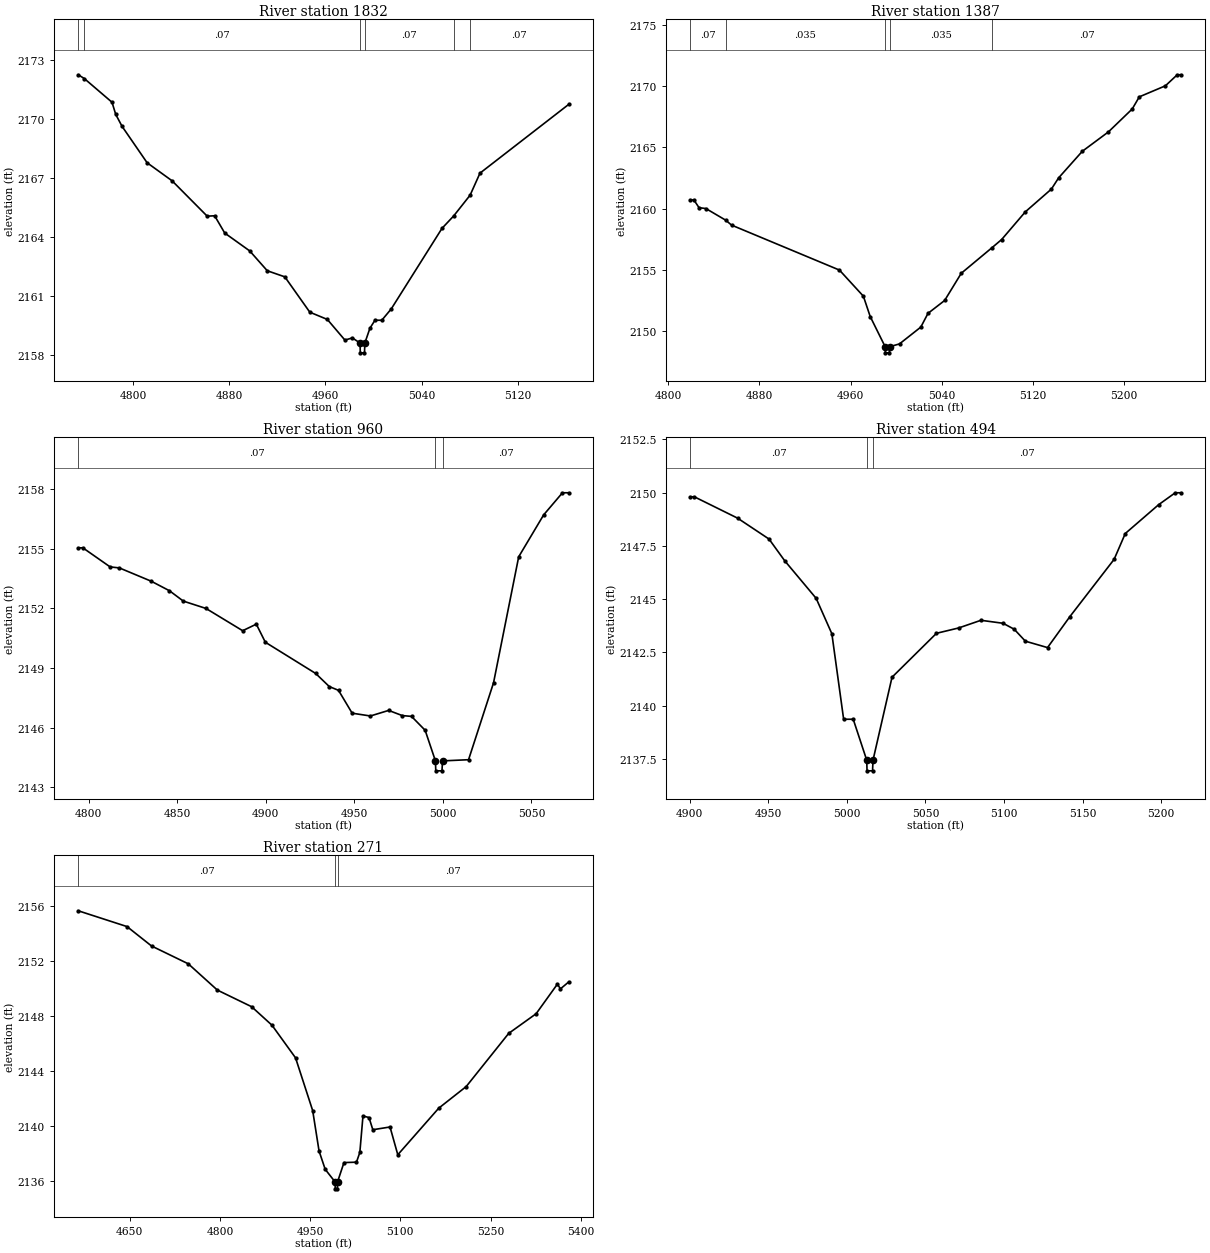
Type RM Length L Ch R = 1,1832,445,445,445
BEGIN DESCRIPTION:
Stream1015 4.0
END DESCRIPTION:
XS GIS Cut Line= 3
      1772975.00     13939375.00      1773175.00     13939225.00
      1773225.00     13939075.01
#Sta/Elev= 30
  4754.3 2172.27  4759.3 2172.08  4782.4 2170.87  4785.5 2170.25  4790.8 2169.64
  4811.6 2167.79  4832.4 2166.87  4861.6 2165.07  4867.8 2165.09  4876.2 2164.21
  4897.0 2163.30  4911.6 2162.29  4926.2 2161.98  4947.0 2160.18  4961.6 2159.81
  4976.2 2158.76  4982.4 2158.87  4988.8 2158.61  4989.0 2158.11  4992.5 2158.11
  4992.8 2158.61  4997.0 2159.36  5001.2 2159.77  5006.9 2159.77  5014.8 2160.35
  5057.0 2164.45  5066.7 2165.08  5080.4 2166.14  5088.6 2167.26  5162.4 2170.76
#Mann=6,-1,0
  4754.3   0.035       0  4759.3    0.07       0  4988.8    0.05       0
  4992.8    0.07       0  5066.7   0.035       0  5080.4    0.07       0
Bank Sta=4988.8,4992.8
Exp/Cntr=0.3,0.1

Type RM Length L Ch R = 1,1387,427,427,427
BEGIN DESCRIPTION:
Stream1015 3.0
END DESCRIPTION:
XS GIS Cut Line= 3
      1773375.01     13939575.00      1773525.00     13939475.00
      1773675.02     13939274.97
#Sta/Elev= 30
  4819.5 2160.72  4822.5 2160.72  4827.0 2160.09  4833.0 2160.02  4850.4 2159.07
  4855.5 2158.67  4950.2 2155.00  4971.2 2152.87  4977.2 2151.21  4990.3 2148.75
  4990.5 2148.25  4994.0 2148.25  4994.3 2148.75  5002.9 2148.98  5021.6 2150.35
  5027.9 2151.47  5042.5 2152.52  5057.1 2154.74  5084.1 2156.83  5092.5 2157.49
  5113.3 2159.75  5136.2 2161.61  5142.5 2162.52  5163.3 2164.69  5186.2 2166.27
  5207.1 2168.14  5213.3 2169.13  5236.2 2170.03  5246.6 2170.93  5249.8 2170.93
#Mann=5,-1,0
  4819.5    0.07       0  4850.4   0.035       0  4990.3   0.035       0
  4994.3   0.035       0  5084.1    0.07       0
Bank Sta=4990.3,4994.3
Exp/Cntr=0.3,0.1

Type RM Length L Ch R = 1,960,466,466,466
BEGIN DESCRIPTION:
Stream1015 2.0
END DESCRIPTION:
XS GIS Cut Line= 3
      1773575.02     13939825.00      1773775.00     13939775.00
      1773824.97     13939725.03
#Sta/Elev= 30
  4794.2 2155.05  4796.8 2155.05  4812.2 2154.09  4817.4 2154.04  4835.4 2153.37
  4845.7 2152.89  4853.5 2152.37  4866.3 2152.00  4887.0 2150.88  4894.7 2151.21
  4899.8 2150.30  4928.2 2148.73  4935.9 2148.07  4941.1 2147.88  4948.8 2146.73
  4959.1 2146.59  4969.4 2146.87  4977.1 2146.61  4982.3 2146.57  4990.0 2145.87
  4995.8 2144.33  4996.0 2143.83  4999.5 2143.83  4999.8 2144.33  5014.5 2144.39
  5028.6 2148.26  5042.8 2154.60  5056.9 2156.71  5067.5 2157.82  5071.0 2157.82
#Mann=3,-1,0
  4794.2    0.07       0  4995.8    0.05       0  4999.8    0.07       0
Bank Sta=4995.8,4999.8
Exp/Cntr=0.3,0.1

Type RM Length L Ch R = 1,494,223,223,223
BEGIN DESCRIPTION:
Stream1015 1.0
END DESCRIPTION:
XS GIS Cut Line= 3
      1773724.97     13940225.00      1773825.00     13940225.00
      1773975.02     13940074.98
#Sta/Elev= 27
  4900.4 2149.80  4902.9 2149.80  4930.4 2148.80  4950.4 2147.82  4960.4 2146.80
  4980.4 2145.04  4990.4 2143.38  4997.9 2139.37  5004.0 2139.37  5012.6 2137.45
  5012.8 2136.95  5016.3 2136.95  5016.6 2137.45  5028.7 2141.34  5057.0 2143.40
  5071.1 2143.65  5085.3 2144.01  5099.4 2143.87  5106.5 2143.59  5113.6 2143.03
  5127.7 2142.73  5141.9 2144.18  5170.1 2146.87  5177.2 2148.08  5198.4 2149.43
  5209.0 2149.99  5212.6 2149.99
#Mann=3,-1,0
  4900.4    0.07       0  5012.6    0.05       0  5016.6    0.07       0
Bank Sta=5012.6,5016.6
Exp/Cntr=0.3,0.1

Type RM Length L Ch R = 1,271,0,0,0
BEGIN DESCRIPTION:
Stream1015 0.0
END DESCRIPTION:
XS GIS Cut Line= 4
      1773525.40     13940409.50      1773754.95     13940454.09
      1774002.41     13940383.89      1774084.29     13940070.06
#Sta/Elev= 30
  4564.5 2155.64  4645.6 2154.49  4686.3 2153.08  4747.5 2151.78  4795.8 2149.87
  4852.8 2148.66  4886.7 2147.31  4925.8 2144.94  4954.3 2141.10  4964.9 2138.16
  4975.1 2136.83  4991.6 2135.91  4991.9 2135.41  4995.4 2135.41  4995.6 2135.91
  5006.3 2137.32  5027.1 2137.35  5032.7 2138.06  5037.9 2140.71  5047.9 2140.60
  5054.3 2139.71  5082.9 2139.91  5095.8 2137.89  5163.9 2141.28  5209.5 2142.85
  5280.2 2146.72  5325.8 2148.15  5361.1 2150.30  5366.3 2149.96  5379.9 2150.46
#Mann=3,-1,0
  4564.5    0.07       0  4991.6    0.05       0  4995.6    0.07       0
Bank Sta=4991.6,4995.6
Exp/Cntr=0.3,0.1

Chan Stop Cuts=-1