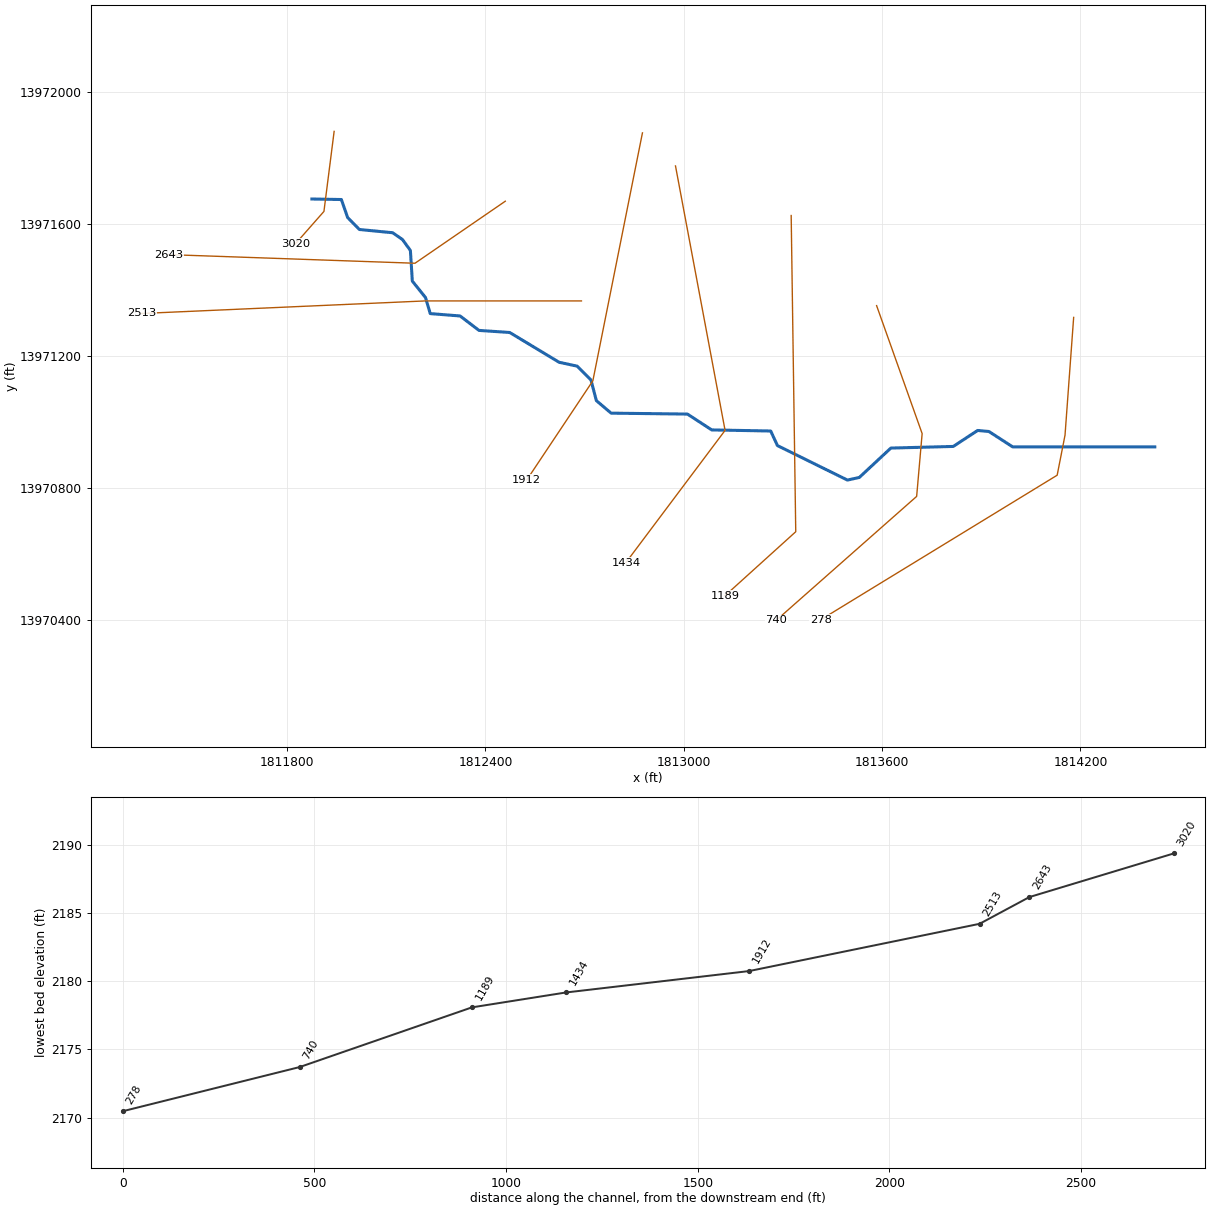
--- Stream1164.prj (project) ---

Proj Title=Stream1164 Base Level Engineering
Current Plan=p01
Default Exp/Contr=0.3,0.1
English Units
Geom File=g01
Flow File=f01
Plan File=p01
Y Axis Title=Elevation
X Axis Title(PF)=Main Channel Distance
X Axis Title(XS)=Station
BEGIN DESCRIPTION:
Stream1164
END DESCRIPTION:
DSS Export Rating Curves= 0
DSS Export Rating Curve Sorted= 0
DSS Export Volume Flow Curves= 0
DXF OffsetX= 0
DXF OffsetY= 0
DXF ScaleX= 1
DXF ScaleY= 10

--- Stream1164.p01 (plan) ---

Plan Title=Multiple Run
Short Identifier=Multiple
Geom File=g01
Flow File=f01
Subcritical Flow
K Sum by GR= 0
Std Step Tol= 0.01
Critical Tol= 0.01
Num of Std Step Trials= 20
Max Error Tol= 0.3
Flow Tol Ratio= 0.001
Split Flow NTrial= 30
Split Flow Tol= 0.02
Split Flow Ratio= 0.02
Log Output Level= 0
Friction Slope Method= 1
Unsteady Friction Slope Method= 2
Unsteady Bridges Friction Slope Method= 1
Parabolic Critical Depth
Global Vel Dist=  1 , 1 , 1
Global Log Level= 0
CheckData=True
Encroach Param= -1, 0, 0, 0
BEGIN DESCRIPTION:
Multiple Run
END DESCRIPTION:

--- Stream1164.f01 (steady flow) ---

Flow Title=Multiple
Program Version=4.10
Number of Profiles= 7
Profile Names=10-year,25-year,50-year,1pct_min,100-year,1pct_plu,500-year
River Rch & RM=Stream1164,Reach-1         ,3020
    1220    2073    2879    1928    3846    7675    6791
Boundary for River Rch & Prof#=Stream1164,Reach-1         , 1
Up Type= 0
Dn Type= 3
Dn Slope=0.008
Boundary for River Rch & Prof#=Stream1164,Reach-1         , 2
Up Type= 0
Dn Type= 3
Dn Slope=0.008
Boundary for River Rch & Prof#=Stream1164,Reach-1         , 3
Up Type= 0
Dn Type= 3
Dn Slope=0.008
Boundary for River Rch & Prof#=Stream1164,Reach-1         , 4
Up Type= 0
Dn Type= 3
Dn Slope=0.008
Boundary for River Rch & Prof#=Stream1164,Reach-1         , 5
Up Type= 0
Dn Type= 3
Dn Slope=0.008
Boundary for River Rch & Prof#=Stream1164,Reach-1         , 6
Up Type= 0
Dn Type= 3
Dn Slope=0.008
Boundary for River Rch & Prof#=Stream1164,Reach-1         , 7
Up Type= 0
Dn Type= 3
Dn Slope=0.008
DSS Import GetInterval= 0
DSS Import GetPeak= 0
DSS Import FillOption= 0

--- Stream1164.g01 (geometry) ---

Geom Title=Existing Conditions

River Reach=Stream1164,Reach-1
Reach XY= 30
      1811875.00     13971675.00      1811964.09     13971673.42
      1811983.12     13971618.93      1812018.56     13971582.79
      1812119.31     13971572.93      1812149.01     13971552.33
      1812172.93     13971519.31      1812178.82     13971426.56
      1812218.70     13971376.78      1812233.02     13971328.31
      1812323.33     13971321.11      1812380.57     13971277.47
      1812473.42     13971271.17      1812622.84     13971181.11
      1812677.55     13971169.27      1812719.24     13971127.51
      1812735.63     13971064.96      1812780.26     13971027.09
      1813011.08     13971024.32      1813084.66     13970976.38
      1813263.05     13970973.08      1813283.36     13970929.07
      1813495.20     13970824.63      1813531.05     13970832.50
      1813626.47     13970921.45      1813815.35     13970926.40
      1813889.10     13970974.76      1813923.26     13970971.63
      1813995.03     13970925.09      1814425.00     13970925.00

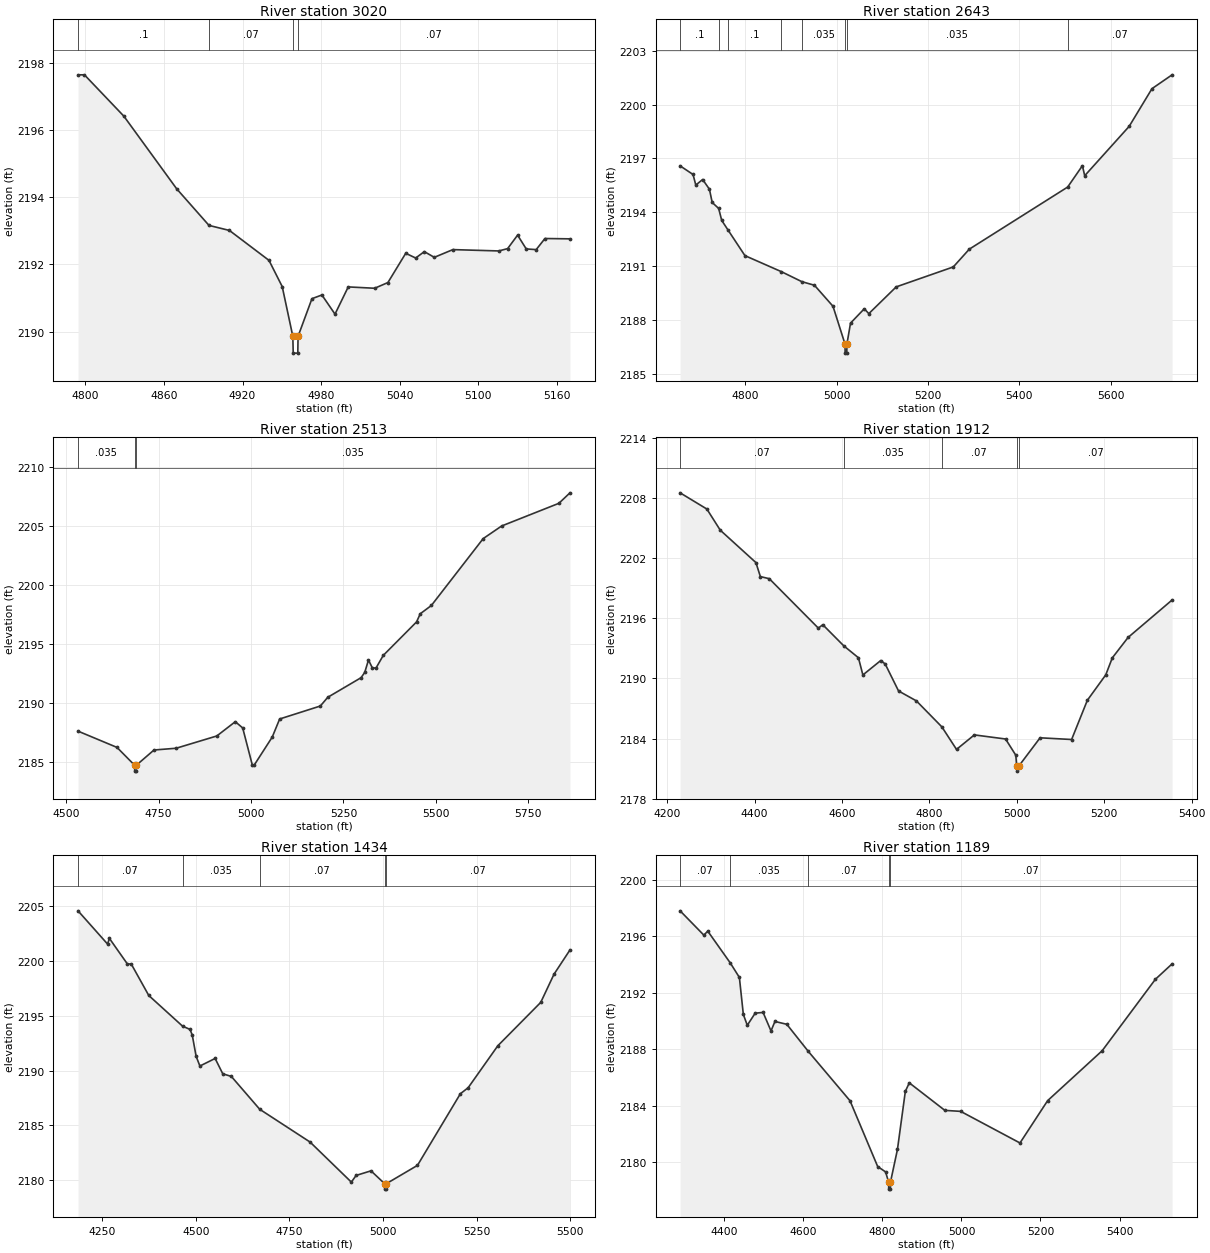
Type RM Length L Ch R = 1,3020,377,377,377
BEGIN DESCRIPTION:
Stream1164 6.0
END DESCRIPTION:
XS GIS Cut Line= 3
      1811942.26     13971879.67      1811911.38     13971637.41
      1811824.54     13971538.83
#Sta/Elev= 30
  4794.4 2197.64  4799.3 2197.64  4829.4 2196.41  4869.7 2194.25  4894.4 2193.16
  4910.0 2193.01  4940.2 2192.12  4950.3 2191.34  4958.4 2189.86  4958.7 2189.36
  4962.2 2189.36  4962.4 2189.86  4973.0 2190.98  4980.6 2191.09  4990.6 2190.52
  5000.7 2191.33  5020.9 2191.29  5031.0 2191.46  5044.6 2192.33  5052.2 2192.19
  5058.8 2192.38  5066.4 2192.21  5080.6 2192.44  5115.7 2192.40  5122.4 2192.47
  5130.0 2192.87  5136.6 2192.46  5144.2 2192.44  5150.9 2192.77  5170.0 2192.76
#Mann=4,-1,0
  4794.4     0.1       0  4894.4    0.07       0  4958.4    0.05       0
  4962.4    0.07       0
Bank Sta=4958.4,4962.4
Exp/Cntr=0.3,0.1

Type RM Length L Ch R = 1,2643,130,130,130
BEGIN DESCRIPTION:
Stream1164 5.0
END DESCRIPTION:
XS GIS Cut Line= 3
      1812460.07     13971668.31      1812186.89     13971480.65
      1811441.07     13971506.78
#Sta/Elev= 30
  4656.8 2196.59  4685.1 2196.11  4691.2 2195.52  4706.1 2195.83  4721.0 2195.29
  4727.1 2194.55  4741.2 2194.22  4748.0 2193.55  4761.4 2193.03  4798.8 2191.59
  4878.4 2190.70  4923.5 2190.14  4951.1 2189.94  4991.7 2188.77  5018.1 2186.66
  5018.3 2186.16  5021.9 2186.16  5022.2 2186.66  5030.1 2187.83  5060.2 2188.63
  5070.2 2188.36  5130.2 2189.85  5255.2 2190.96  5290.3 2191.95  5505.8 2195.41
  5538.1 2196.60  5543.1 2196.04  5640.5 2198.79  5690.5 2200.89  5734.5 2201.66
#Mann=8,-1,0
  4656.8     0.1       0  4741.2    0.07       0  4761.4     0.1       0
  4878.4    0.07       0  4923.5   0.035       0  5018.1   0.035       0
  5022.2   0.035       0  5505.8    0.07       0
Bank Sta=5018.1,5022.2
Exp/Cntr=0.3,0.1

Type RM Length L Ch R = 1,2513,601,601,601
BEGIN DESCRIPTION:
Stream1164 4.0
END DESCRIPTION:
XS GIS Cut Line= 3
      1812690.45     13971366.65      1812217.77     13971366.65
      1811360.39     13971328.65
#Sta/Elev= 30
  4532.0 2187.59  4637.5 2186.21  4685.1 2184.70  4685.5 2184.20  4689.5 2184.20
  4689.8 2184.70  4737.5 2185.99  4797.5 2186.14  4907.5 2187.18  4957.5 2188.39
  4977.5 2187.86  5003.6 2184.71  5008.6 2184.71  5057.5 2187.09  5077.5 2188.62
  5187.6 2189.72  5207.7 2190.46  5297.7 2192.12  5307.7 2192.57  5317.8 2193.62
  5327.8 2192.98  5337.8 2192.92  5357.8 2194.01  5447.9 2196.85  5457.9 2197.54
  5487.9 2198.24  5628.1 2203.91  5678.1 2204.98  5832.8 2206.90  5862.9 2207.79
#Mann=3,-1,0
  4532.0   0.035       0  4685.1   0.035       0  4689.8   0.035       0
Bank Sta=4685.1,4689.8
Exp/Cntr=0.3,0.1

Type RM Length L Ch R = 1,1912,478,478,478
BEGIN DESCRIPTION:
Stream1164 3.0
END DESCRIPTION:
XS GIS Cut Line= 3
      1812875.01     13971875.03      1812725.00     13971125.00
      1812525.02     13970825.03
#Sta/Elev= 30
  4229.8 2208.55  4291.0 2206.93  4321.6 2204.82  4403.2 2201.58  4413.4 2200.18
  4433.8 2199.97  4546.0 2195.03  4556.2 2195.37  4604.2 2193.26  4637.7 2192.07
  4647.9 2190.35  4688.7 2191.79  4698.9 2191.45  4729.5 2188.75  4770.3 2187.76
  4828.6 2185.16  4862.1 2182.91  4902.9 2184.36  4974.3 2183.95  4997.7 2182.33
  4999.8 2181.24  5000.2 2180.74  5004.5 2181.24  5053.3 2184.07  5125.4 2183.90
  5161.4 2187.82  5203.5 2190.36  5218.5 2192.06  5254.6 2194.10  5355.2 2197.84
#Mann=5,-1,0
  4229.8    0.07       0  4604.2   0.035       0  4828.6    0.07       0
  4999.8    0.05       0  5004.5    0.07       0
Bank Sta=4999.8,5004.5
Exp/Cntr=0.3,0.1

Type RM Length L Ch R = 1,1434,245,245,245
BEGIN DESCRIPTION:
Stream1164 2.0
END DESCRIPTION:
XS GIS Cut Line= 3
      1812975.01     13971774.96      1813125.00     13970975.00
      1812825.00     13970575.00
#Sta/Elev= 30
  4185.6 2204.58  4264.4 2201.55  4269.5 2202.06  4317.0 2199.75  4328.0 2199.71
  4374.6 2196.85  4464.8 2194.05  4484.9 2193.75  4490.8 2193.22  4501.0 2191.30
  4511.1 2190.41  4551.8 2191.10  4572.2 2189.70  4595.1 2189.46  4670.9 2186.46
  4805.3 2183.47  4915.6 2179.81  4928.3 2180.42  4968.1 2180.84  5004.4 2179.67
  5004.7 2179.17  5008.8 2179.17  5009.2 2179.67  5092.2 2181.34  5206.8 2187.88
  5227.6 2188.43  5306.8 2192.26  5421.4 2196.22  5456.8 2198.79  5499.5 2201.01
#Mann=5,-1,0
  4185.6    0.07       0  4464.8   0.035       0  4670.9    0.07       0
  5004.4    0.05       0  5009.2    0.07       0
Bank Sta=5004.4,5009.2
Exp/Cntr=0.3,0.1

Type RM Length L Ch R = 1,1189,449,449,449
BEGIN DESCRIPTION:
Stream1164 1.0
END DESCRIPTION:
XS GIS Cut Line= 3
      1813325.00     13971624.96      1813338.82     13970668.37
      1813124.99     13970474.99
#Sta/Elev= 30
  4288.0 2197.80  4348.0 2196.08  4358.0 2196.36  4414.9 2194.11  4438.0 2193.08
  4448.0 2190.46  4458.0 2189.69  4478.0 2190.55  4498.0 2190.60  4518.0 2189.29
  4528.0 2189.96  4558.0 2189.76  4612.4 2187.84  4718.0 2184.34  4788.0 2179.68
  4808.0 2179.30  4815.6 2178.58  4816.0 2178.08  4820.1 2178.08  4820.4 2178.58
  4838.0 2180.89  4858.0 2185.01  4868.0 2185.61  4958.0 2183.66  4998.0 2183.59
  5148.1 2181.35  5218.1 2184.35  5356.2 2187.89  5490.8 2192.95  5533.0 2194.04
#Mann=5,-1,0
  4288.0    0.07       0  4414.9   0.035       0  4612.4    0.07       0
  4815.6    0.05       0  4820.4    0.07       0
Bank Sta=4815.6,4820.4
Exp/Cntr=0.3,0.1

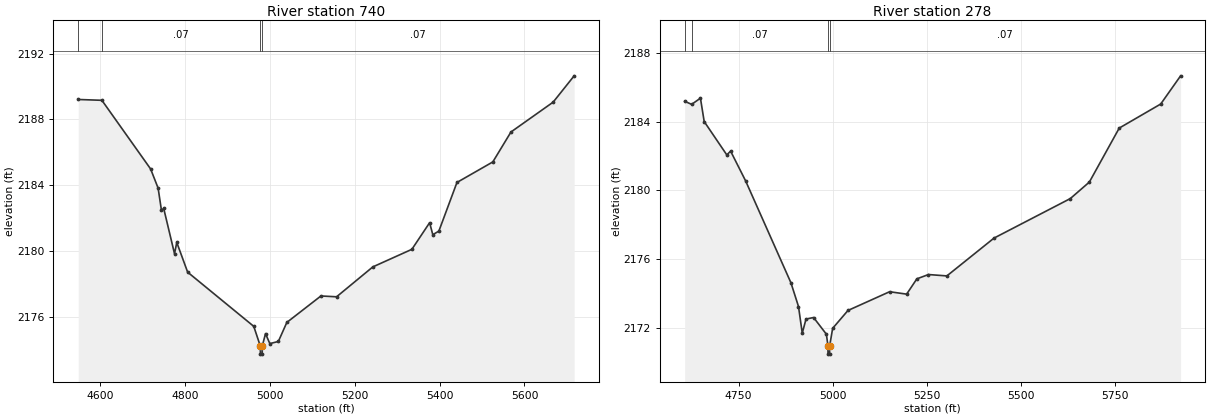
Type RM Length L Ch R = 1,740,462,462,462
BEGIN DESCRIPTION:
Stream1164 0.0
END DESCRIPTION:
XS GIS Cut Line= 4
      1813583.44     13971352.44      1813721.21     13970965.26
      1813704.59     13970775.25      1813279.72     13970400.23
#Sta/Elev= 30
  4548.7 2189.21  4604.5 2189.16  4719.3 2184.98  4737.0 2183.81  4744.8 2182.46
  4750.1 2182.58  4775.6 2179.82  4780.9 2180.51  4806.5 2178.70  4962.3 2175.40
  4977.6 2174.21  4978.0 2173.71  4982.1 2173.71  4982.4 2174.21  4990.0 2174.96
  5000.1 2174.35  5020.2 2174.48  5040.2 2175.64  5120.5 2177.25  5157.4 2177.20
  5242.8 2179.02  5334.8 2180.09  5376.6 2181.71  5384.1 2180.98  5398.4 2181.20
  5441.0 2184.16  5525.5 2185.41  5568.2 2187.23  5667.7 2189.05  5717.1 2190.65
#Mann=4,-1,0
  4548.7   0.035       0  4604.5    0.07       0  4977.6    0.05       0
  4982.4    0.07       0
Bank Sta=4977.6,4982.4
Exp/Cntr=0.3,0.1

Type RM Length L Ch R = 1,278,0,0,0
BEGIN DESCRIPTION:
Stream1164 0.1
END DESCRIPTION:
XS GIS Cut Line= 4
      1814179.61     13971316.75      1814153.48     13970960.51
      1814129.73     13970839.38      1813414.85     13970402.37
#Sta/Elev= 30
  4606.6 2185.18  4625.1 2185.00  4648.5 2185.36  4658.5 2184.00  4718.6 2182.06
  4728.7 2182.28  4768.8 2180.54  4889.1 2174.62  4909.2 2173.24  4919.2 2171.69
  4929.2 2172.51  4949.3 2172.60  4983.3 2171.63  4987.4 2170.97  4987.7 2170.47
  4991.8 2170.47  4992.2 2170.97  5000.0 2171.97  5040.7 2173.01  5151.4 2174.10
  5196.7 2173.96  5223.9 2174.85  5254.8 2175.10  5303.7 2175.02  5429.0 2177.22
  5631.9 2179.52  5682.5 2180.48  5761.9 2183.62  5872.2 2185.02  5925.1 2186.66
#Mann=4,-1,0
  4606.6   0.035       0  4625.1    0.07       0  4987.4    0.05       0
  4992.2    0.07       0
Bank Sta=4987.4,4992.2
Exp/Cntr=0.3,0.1

Chan Stop Cuts=-1