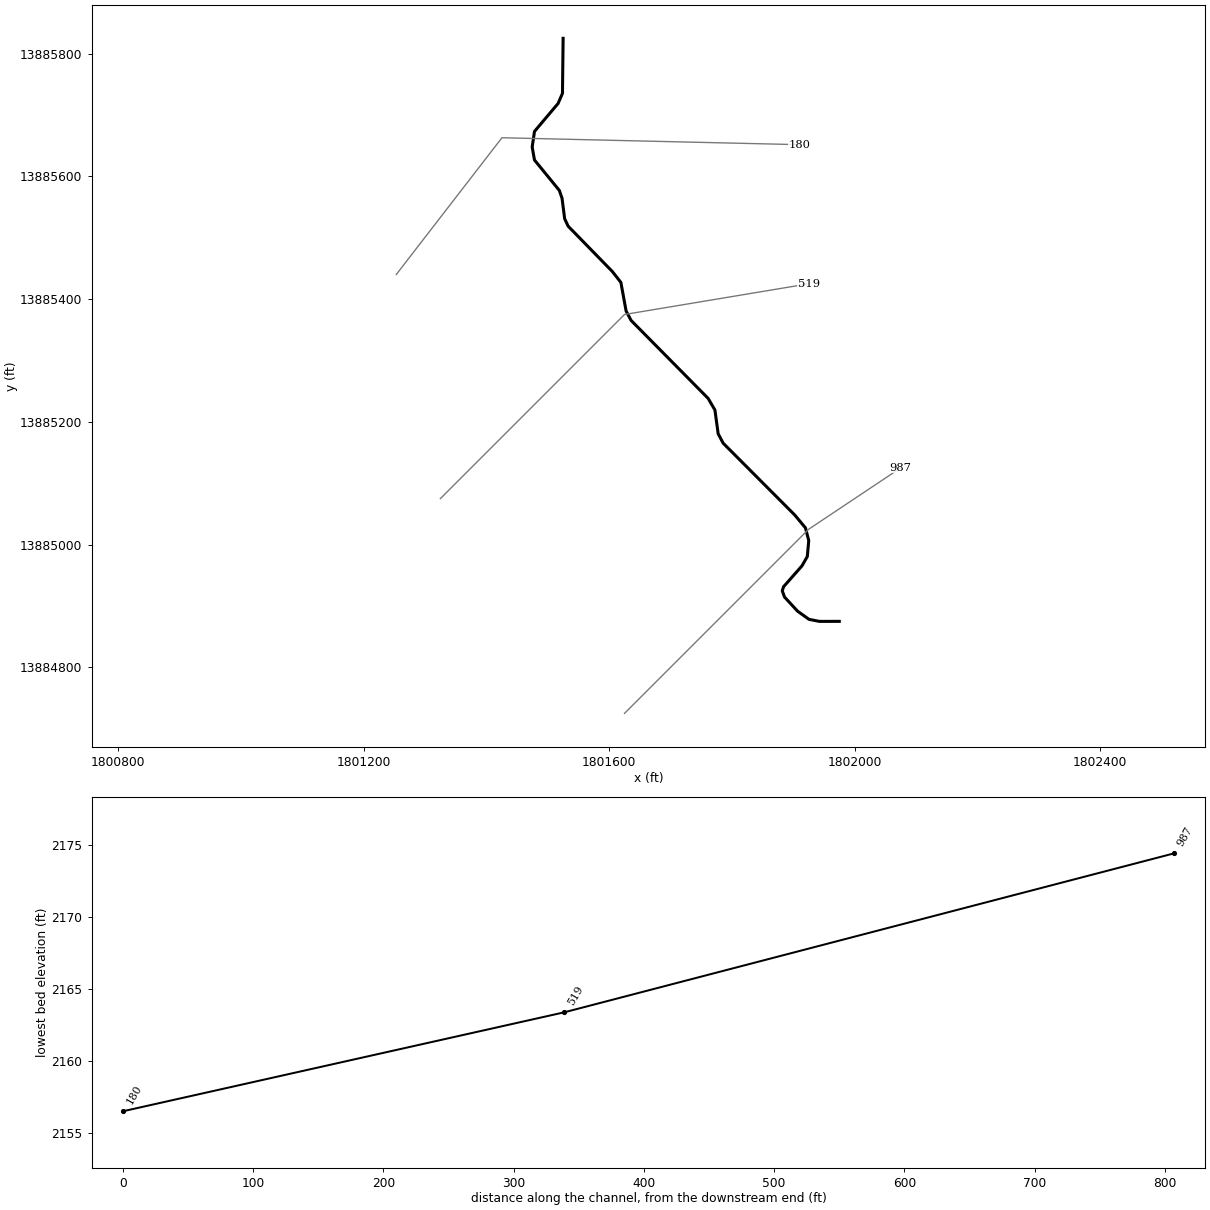
--- Stream1232.prj (project) ---

Proj Title=Stream1232 Base Level Engineering
Current Plan=p01
Default Exp/Contr=0.3,0.1
English Units
Geom File=g01
Flow File=f01
Plan File=p01
BEGIN DESCRIPTION:
Stream1232
END DESCRIPTION:

--- Stream1232.p01 (plan) ---

Plan Title=Multiple Run
Short Identifier=Multiple
Geom File=g01
Flow File=f01
Subcritical Flow
K Sum by GR= 0
Std Step Tol= 0.01
Critical Tol= 0.01
Num of Std Step Trials= 20
Max Error Tol= 0.3
Flow Tol Ratio= 0.001
Split Flow NTrial= 30
Split Flow Tol= 0.02
Split Flow Ratio= 0.02
Log Output Level= 0
Friction Slope Method= 1
Unsteady Friction Slope Method= 2
Unsteady Bridges Friction Slope Method= 1
Parabolic Critical Depth
Global Vel Dist=  1 , 1 , 1
Global Log Level= 0
CheckData=True
Encroach Param= -1, 0, 0, 0
BEGIN DESCRIPTION:
Multiple Run
END DESCRIPTION:

--- Stream1232.f01 (steady flow) ---

Flow Title=Multiple
Number of Profiles=7
Profile Names=10-year,25-year,50-year,1pct_min,100-year,1pct_plu,500-year
River Rch & RM= Stream1232,Reach-1,987
     519     849    1150     755    1507    3007    2556
Boundary for River Rch & Prof#=Stream1232,Reach-1,1
Up Type=0
Dn Type=3
Dn Slope=0.005
Boundary for River Rch & Prof#=Stream1232,Reach-1,2
Up Type=0
Dn Type=3
Dn Slope=0.005
Boundary for River Rch & Prof#=Stream1232,Reach-1,3
Up Type=0
Dn Type=3
Dn Slope=0.005
Boundary for River Rch & Prof#=Stream1232,Reach-1,4
Up Type=0
Dn Type=3
Dn Slope=0.005
Boundary for River Rch & Prof#=Stream1232,Reach-1,5
Up Type=0
Dn Type=3
Dn Slope=0.005
Boundary for River Rch & Prof#=Stream1232,Reach-1,6
Up Type=0
Dn Type=3
Dn Slope=0.005
Boundary for River Rch & Prof#=Stream1232,Reach-1,7
Up Type=0
Dn Type=3
Dn Slope=0.005

--- Stream1232.g01 (geometry) ---

Geom Title=Existing Conditions

River Reach=Stream1232,Reach-1
Reach XY= 30
      1801975.00     13884875.00      1801942.74     13884874.92
      1801925.63     13884878.27      1801907.05     13884891.56
      1801885.72     13884914.69      1801882.12     13884924.74
      1801884.22     13884931.42      1801914.10     13884965.30
      1801922.90     13884980.63      1801925.24     13885006.59
      1801919.89     13885027.29      1801902.28     13885048.46
      1801785.78     13885165.32      1801777.64     13885180.64
      1801772.36     13885219.36      1801761.37     13885238.21
      1801635.78     13885365.32      1801627.64     13885380.64
      1801619.13     13885427.28      1801605.17     13885445.07
      1801533.15     13885518.95      1801527.50     13885531.04
      1801523.26     13885564.30      1801518.82     13885577.19
      1801478.34     13885626.72      1801474.60     13885647.80
      1801478.33     13885673.27      1801516.83     13885718.91
      1801523.95     13885735.41      1801525.00     13885825.00

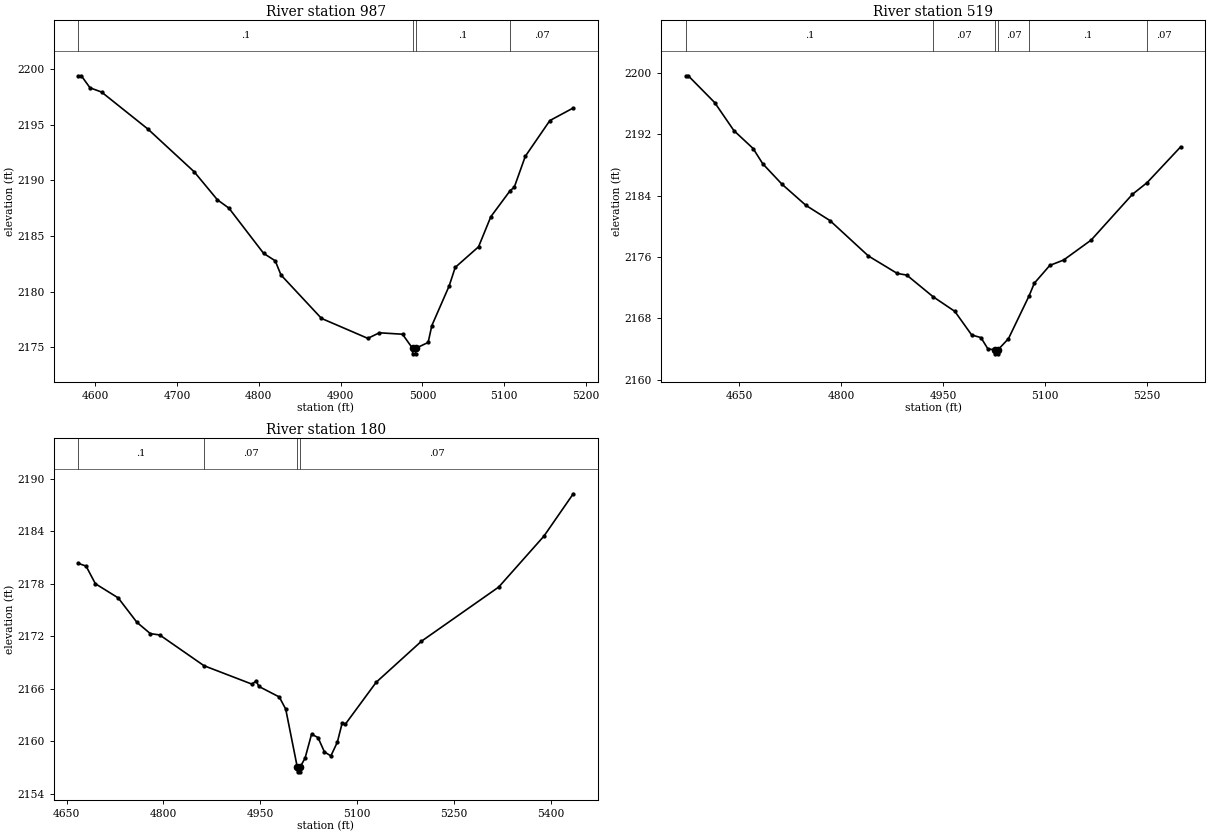
Type RM Length L Ch R = 1,987,468,468,468
BEGIN DESCRIPTION:
Stream0232 2.0
END DESCRIPTION:
XS GIS Cut Line= 3
      1801625.04     13884725.04      1801925.00     13885025.00
      1802075.01     13885125.00
#Sta/Elev= 30
  4579.7 2199.39  4583.2 2199.39  4593.8 2198.31  4607.9 2197.93  4664.5 2194.61
  4721.1 2190.77  4749.4 2188.26  4763.5 2187.51  4805.9 2183.45  4820.1 2182.78
  4827.1 2181.51  4876.6 2177.61  4933.2 2175.82  4947.3 2176.32  4975.6 2176.19
  4987.8 2174.93  4988.0 2174.43  4991.5 2174.43  4991.8 2174.93  5006.9 2175.45
  5011.4 2176.96  5032.5 2180.51  5040.0 2182.19  5068.5 2184.04  5083.5 2186.74
  5107.1 2189.08  5112.1 2189.38  5125.6 2192.16  5155.6 2195.37  5184.2 2196.50
#Mann=4,-1,0
  4579.7     0.1       0  4987.8    0.05       0  4991.8     0.1       0
  5107.1    0.07       0
Bank Sta=4987.8,4991.8
Exp/Cntr=0.3,0.1

Type RM Length L Ch R = 1,519,339,339,339
BEGIN DESCRIPTION:
Stream0232 1.0
END DESCRIPTION:
XS GIS Cut Line= 3
      1801325.03     13885075.03      1801625.00     13885375.00
      1801925.03     13885425.01
#Sta/Elev= 30
  4571.3 2199.59  4574.8 2199.59  4613.7 2196.10  4642.0 2192.45  4670.3 2190.12
  4684.4 2188.14  4712.7 2185.48  4748.0 2182.72  4783.4 2180.74  4840.0 2176.13
  4882.4 2173.86  4896.5 2173.64  4935.3 2170.82  4967.2 2168.92  4992.0 2165.85
  5005.7 2165.50  5015.8 2164.05  5026.5 2163.89  5026.7 2163.39  5030.2 2163.39
  5030.5 2163.89  5046.2 2165.37  5076.6 2170.95  5084.2 2172.58  5107.0 2174.90
  5127.3 2175.60  5167.9 2178.20  5228.7 2184.16  5250.3 2185.68  5299.7 2190.34
#Mann=6,-1,0
  4571.3     0.1       0  4935.3    0.07       0  5026.5    0.05       0
  5030.5    0.07       0  5076.6     0.1       0  5250.3    0.07       0
Bank Sta=5026.5,5030.5
Exp/Cntr=0.3,0.1

Type RM Length L Ch R = 1,180,0,0,0
BEGIN DESCRIPTION:
Stream0232 0.0
END DESCRIPTION:
XS GIS Cut Line= 3
      1801253.17     13885440.24      1801425.33     13885663.02
      1801910.45     13885651.72
#Sta/Elev= 30
  4668.4 2180.31  4680.2 2180.00  4694.6 2177.99  4730.0 2176.37  4759.0 2173.58
  4779.8 2172.29  4794.3 2172.14  4862.9 2168.63  4937.4 2166.52  4943.7 2166.90
  4948.0 2166.26  4979.6 2165.06  4989.6 2163.67  5007.6 2157.01  5007.9 2156.51
  5011.4 2156.51  5011.6 2157.01  5019.6 2158.08  5029.6 2160.80  5039.6 2160.43
  5049.6 2158.78  5059.6 2158.33  5069.6 2159.90  5077.1 2162.09  5082.1 2161.96
  5129.7 2166.73  5199.7 2171.41  5319.7 2177.61  5389.7 2183.42  5435.2 2188.26
#Mann=4,-1,0
  4668.4     0.1       0  4862.9    0.07       0  5007.6    0.05       0
  5011.6    0.07       0
Bank Sta=5007.6,5011.6
Exp/Cntr=0.3,0.1

Chan Stop Cuts=-1