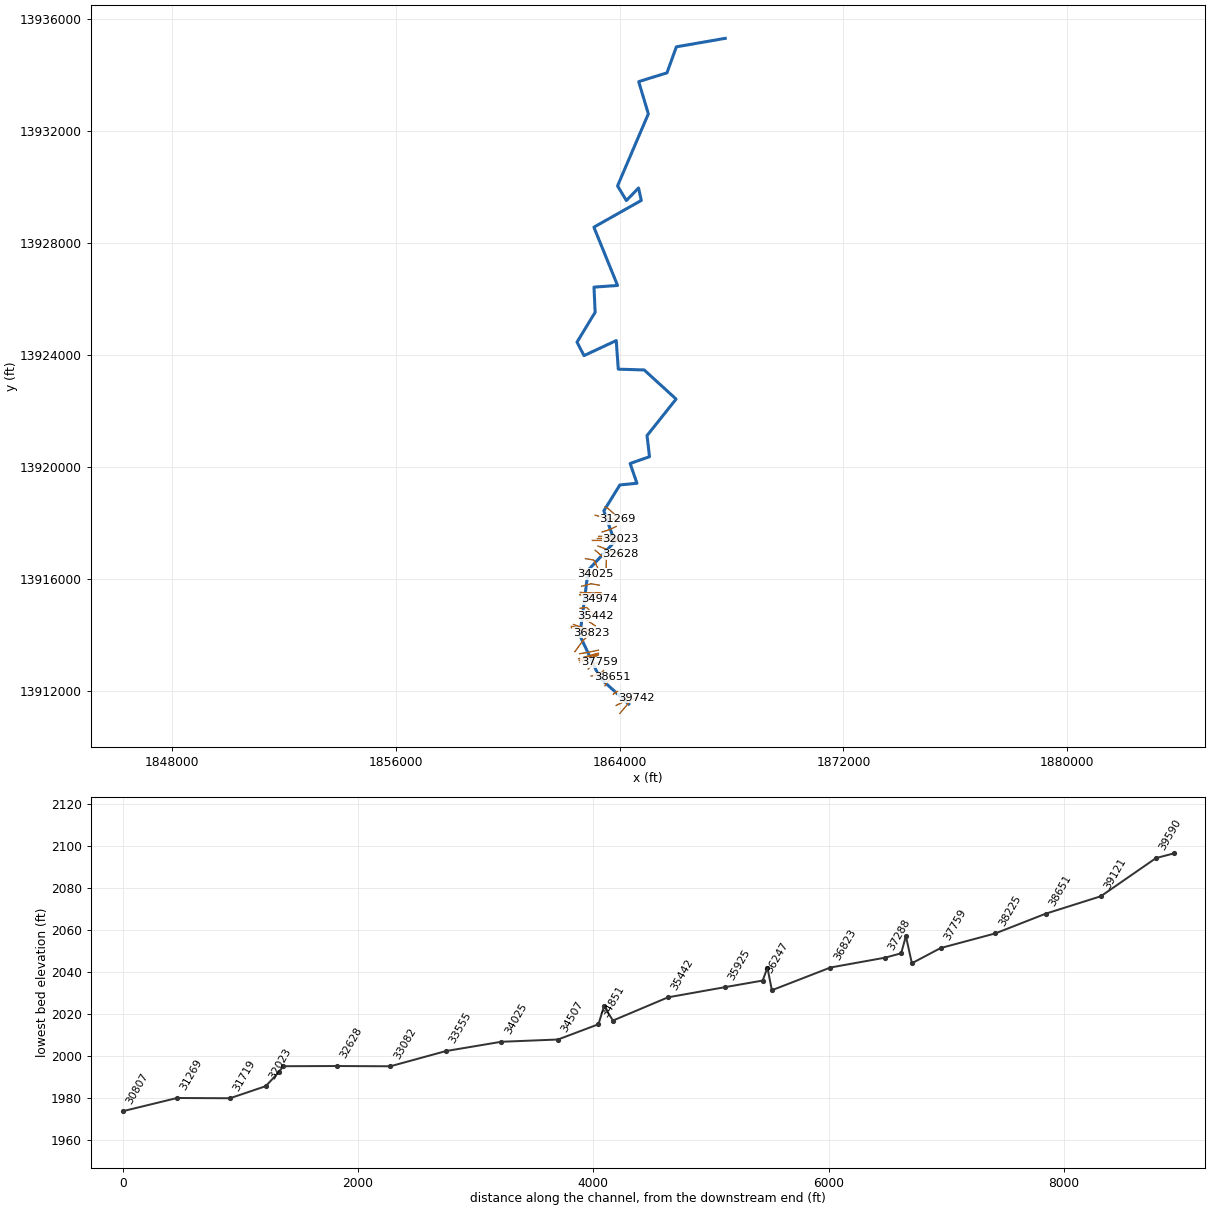
--- Tegener Creek.prj (project) ---

Proj Title=Tegener Creek Base Level Engineering
Current Plan=p01
Default Exp/Contr=0.3,0.1
English Units
Geom File=g01
Flow File=f01
Plan File=p01
Y Axis Title=Elevation
X Axis Title(PF)=Main Channel Distance
X Axis Title(XS)=Station
BEGIN DESCRIPTION:
Tegener Creek
END DESCRIPTION:
DSS Export Rating Curves= 0
DSS Export Rating Curve Sorted= 0
DSS Export Volume Flow Curves= 0
DXF OffsetX= 0
DXF OffsetY= 0
DXF ScaleX= 1
DXF ScaleY= 10

--- Tegener Creek.p01 (plan) ---

Plan Title=Multiple Run
Short Identifier=Multiple
Geom File=g01
Flow File=f01
Subcritical Flow
K Sum by GR= 0
Std Step Tol= 0.01
Critical Tol= 0.01
Num of Std Step Trials= 20
Max Error Tol= 0.3
Flow Tol Ratio= 0.001
Split Flow NTrial= 30
Split Flow Tol= 0.02
Split Flow Ratio= 0.02
Log Output Level= 0
Friction Slope Method= 1
Unsteady Friction Slope Method= 2
Unsteady Bridges Friction Slope Method= 1
Parabolic Critical Depth
Global Vel Dist=  1 , 1 , 1
Global Log Level= 0
CheckData=True
Encroach Param= -1, 0, 0, 0
BEGIN DESCRIPTION:
Multiple Run
END DESCRIPTION:

--- Tegener Creek.f01 (steady flow) ---

Flow Title=Multiple
Number of Profiles=7
Profile Names=10-year,25-year,50-year,1pct_min,100-year,1pct_plu,500-year
River Rch & RM= Tegener Creek,Reach-1,39742
     970    1645    2284    1534    3061    6107    5427
River Rch & RM= Tegener Creek,Reach-1,36325
    1730    3019    4271    2915    5816   11605   10663
River Rch & RM= Tegener Creek,Reach-1,28091
    1866    3270    4639    3175    6334   12638   11674
River Rch & RM= Tegener Creek,Reach-1,26939
    3390    6104    8818    6130   12231   24403   23282
River Rch & RM= Tegener Creek,Reach-1,17717
    3534    6355    9171    6366   12702   25344   24110
River Rch & RM= Tegener Creek,Reach-1,9375
    3826    6896    9966    6926   13819   27572   26290
River Rch & RM= Tegener Creek,Reach-1,5550
    4179    7554   10938    7614   15192   30312   28998
Boundary for River Rch & Prof#=Tegener Creek,Reach-1,1
Up Type=0
Dn Type=3
Dn Slope=0.005
Boundary for River Rch & Prof#=Tegener Creek,Reach-1,2
Up Type=0
Dn Type=3
Dn Slope=0.005
Boundary for River Rch & Prof#=Tegener Creek,Reach-1,3
Up Type=0
Dn Type=3
Dn Slope=0.005
Boundary for River Rch & Prof#=Tegener Creek,Reach-1,4
Up Type=0
Dn Type=3
Dn Slope=0.005
Boundary for River Rch & Prof#=Tegener Creek,Reach-1,5
Up Type=0
Dn Type=3
Dn Slope=0.005
Boundary for River Rch & Prof#=Tegener Creek,Reach-1,6
Up Type=0
Dn Type=3
Dn Slope=0.005
Boundary for River Rch & Prof#=Tegener Creek,Reach-1,7
Up Type=0
Dn Type=3
Dn Slope=0.005

--- Tegener Creek.g01 (geometry) ---

Geom Title=Existing Conditions
Program Version=4.10

River Reach=Tegener Creek   ,Reach-1
Reach XY= 30
        1864325.       13911525.      1863282.85     13912468.81
      1862577.16     13913980.98       1862876.1     13916314.45
      1863823.04     13917330.89      1863434.12     13918431.76
      1864007.92     13919358.85      1864617.66     13919418.61
        1864375.       13920125.      1865066.87     13920368.93
      1864978.67     13921123.42      1866017.32      13922428.7
      1864877.45     13923469.54      1863950.98     13923497.66
      1863877.45     13924519.54        1862725.      13923982.5
      1862475.65     13924464.36      1863122.76     13925530.93
       1863082.8     13926431.21      1863924.77     13926490.21
      1863078.55     13928573.53      1864773.38     13929531.03
        1864675.       13929975.      1864240.21     13929525.23
      1863924.38     13930050.09        1865025.       13932625.
      1864680.52     13933777.43      1865691.77     13934091.43
      1866026.53     13935021.27        1867775.       13935325.

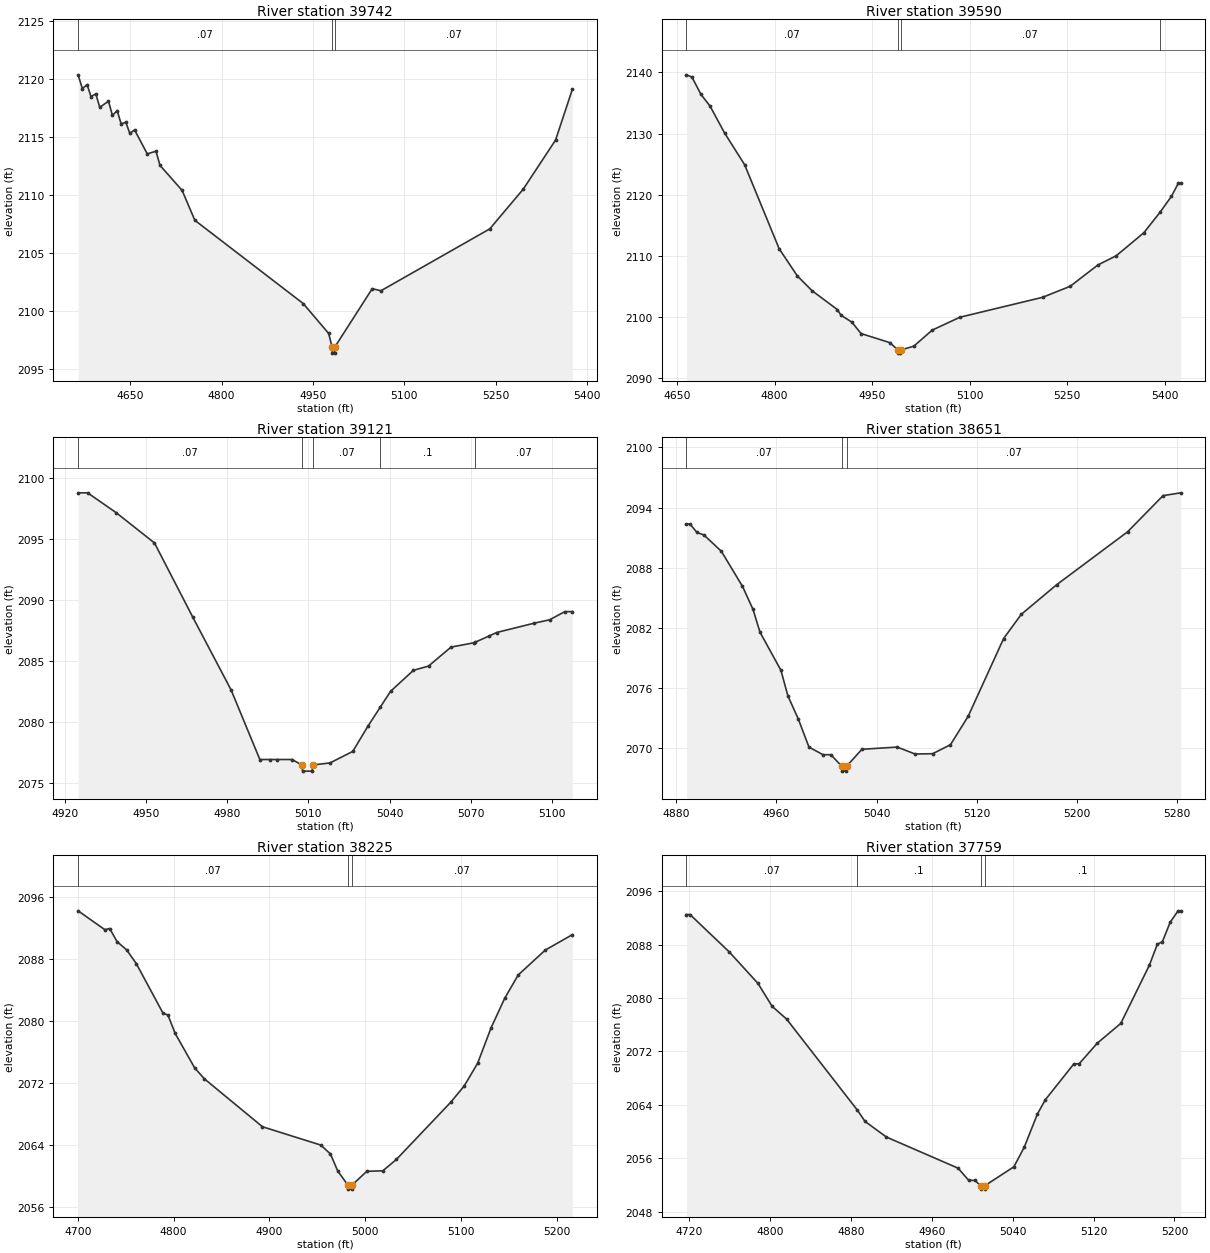
Type RM Length L Ch R = 1 ,39742   ,152,152,152
BEGIN DESCRIPTION:
Tegener Creek 81.0
END DESCRIPTION:
XS GIS Cut Line= 3
      1864007.53     13911192.38      1864413.37     13911674.16
      1864578.19     13911750.07
#Sta/Elev= 30
  4564.5 2120.37  4571.4 2119.18  4579.2 2119.52  4585.7 2118.49  4593.5 2118.73
    4600 2117.57  4614.3 2118.09  4620.8 2116.87  4628.6 2117.28  4635.1 2116.14
  4642.9 2116.27  4649.4 2115.31  4657.2 2115.62    4678 2113.55  4692.3 2113.78
  4698.9 2112.56  4735.2  2110.4  4756.1 2107.82    4934 2100.64  4975.8 2098.06
  4981.6 2096.86  4981.9 2096.36  4985.4 2096.36  4985.6 2096.86  5047.3 2101.92
  5061.6 2101.74  5240.3 2107.08  5295.3 2110.51  5348.3 2114.74  5375.9 2119.12
#Mann= 3 ,-1 , 0
  4564.5     .07       0  4981.6     .05       0  4985.6     .07       0
Bank Sta=4981.6,4985.6
XS Rating Curve= 0 ,0
Exp/Cntr=0.3,0.1

Type RM Length L Ch R = 1 ,39590   ,469,469,469
BEGIN DESCRIPTION:
Tegner Creek 80.0
END DESCRIPTION:
XS GIS Cut Line= 3
      1863875.02     13911475.01        1864175.       13911625.
      1864475.03     13911925.03
#Sta/Elev= 30
  4664.6  2139.6    4673 2139.23  4686.9  2136.4  4700.9 2134.48  4723.3 2130.08
    4754 2124.92  4807.1 2111.19  4835.1 2106.74  4857.4 2104.36  4896.6 2101.25
  4902.2 2100.32  4918.9  2099.2  4932.9 2097.34  4977.6 2095.84  4989.6 2094.64
  4989.9 2094.14  4993.4 2094.14  4993.6 2094.64  5014.1 2095.28  5042.4  2097.9
  5084.8    2100  5212.1 2103.26  5254.5 2105.06    5297 2108.54  5325.3 2110.05
  5367.7 2113.81  5392.6 2117.16  5410.1 2119.76  5420.7  2121.9  5424.3  2121.9
#Mann= 4 ,-1 , 0
  4664.6     .07       0  4989.6     .05       0  4993.6     .07       0
  5392.6      .1       0
Bank Sta=4989.6,4993.6
XS Rating Curve= 0 ,0
Exp/Cntr=0.3,0.1

Type RM Length L Ch R = 1 ,39121   ,470,470,470
BEGIN DESCRIPTION:
Tegner Creek 79.0
END DESCRIPTION:
XS GIS Cut Line= 3
      1863775.03     13911875.03        1863825.       13911925.
      1863925.03     13911975.02
#Sta/Elev= 30
    4925 2098.75  4928.5 2098.75  4939.1 2097.12  4953.2 2094.65  4967.4 2088.56
  4981.5 2082.63  4992.1 2076.95  4995.7 2076.95  4998.5 2076.95    5004 2076.95
  5007.6  2076.5  5007.9    2076  5011.4    2076  5011.6  2076.5    5018 2076.67
  5026.4 2077.61    5032 2079.67  5036.6 2081.24  5040.4 2082.53  5048.8 2084.24
  5054.4 2084.59  5062.7 2086.14  5071.1 2086.49  5071.6 2086.54  5076.7 2087.04
  5079.5 2087.33  5093.5  2088.1  5099.1 2088.37  5104.7 2089.04  5107.5 2089.04
#Mann= 5 ,-1 , 0
    4925     .07       0  5007.6     .05       0  5011.6     .07       0
  5036.6      .1       0  5071.6     .07       0
Bank Sta=5007.6,5011.6
XS Rating Curve= 0 ,0
Exp/Cntr=0.3,0.1

Type RM Length L Ch R = 1 ,38651   ,426,426,426
BEGIN DESCRIPTION:
Tegner Creek 78.0
END DESCRIPTION:
XS GIS Cut Line= 3
      1863475.01     13912175.03        1863525.       13912275.
      1863724.99     13912474.99
#Sta/Elev= 30
  4888.2 2092.36    4891 2092.36  4896.6 2091.51  4902.1 2091.27  4916.1 2089.63
  4932.9 2086.14  4941.3 2083.85  4946.9 2081.56  4963.6 2077.76  4969.2  2075.2
  4977.6 2072.86    4986 2070.09  4997.2 2069.33  5003.5 2069.33  5012.1 2068.19
  5012.4 2067.69  5015.9 2067.69  5016.1 2068.19  5028.3 2069.87  5056.5 2070.09
  5070.7  2069.4  5084.8 2069.43    5099 2070.33  5113.1 2073.16  5141.4 2080.92
  5155.5 2083.34  5183.8  2086.3  5240.4 2091.58  5268.7 2095.19  5282.8 2095.47
#Mann= 3 ,-1 , 0
  4888.2     .07       0  5012.1     .05       0  5016.1     .07       0
Bank Sta=5012.1,5016.1
XS Rating Curve= 0 ,0
Exp/Cntr=0.3,0.1

Type RM Length L Ch R = 1 ,38225   ,466,466,466
BEGIN DESCRIPTION:
Tegner Creek 77.0
END DESCRIPTION:
XS GIS Cut Line= 3
      1862974.98       13912525.        1863275.       13912575.
      1863425.01     13912725.01
#Sta/Elev= 30
  4700.2 2094.24  4728.1 2091.81  4733.2 2091.96  4740.8 2090.28  4750.9  2089.2
    4761 2087.43  4788.9 2081.04    4794 2080.81  4801.6 2078.43  4821.9    2074
    4832 2072.59  4892.8  2066.4  4953.7 2064.04  4963.8 2062.89  4971.4  2060.7
  4982.1 2058.86  4982.3 2058.36  4985.8 2058.36  4986.1 2058.86  5001.8 2060.66
  5018.5 2060.72  5032.6 2062.18  5089.2 2069.53  5103.4 2071.64  5117.5 2074.58
  5131.6 2079.16  5145.8 2082.96  5159.9 2085.97  5188.2 2089.18  5216.5 2091.17
#Mann= 3 ,-1 , 0
  4700.2     .07       0  4982.1     .05       0  4986.1     .07       0
Bank Sta=4982.1,4986.1
XS Rating Curve= 0 ,0
Exp/Cntr=0.3,0.1

Type RM Length L Ch R = 1 ,37759   ,244,244,244
BEGIN DESCRIPTION:
Tegner Creek 76.0
END DESCRIPTION:
XS GIS Cut Line= 3
      1862875.03     13912775.03        1863075.       13912975.
      1863275.04     13913025.01
#Sta/Elev= 30
  4717.2 2092.49  4720.7 2092.49  4759.6 2086.88  4787.9 2082.19    4802 2078.74
  4816.2 2076.85  4886.1 2063.25  4893.9 2061.52  4915.1 2059.18  4985.9 2054.53
  4996.5  2052.7  5002.6  2052.7  5008.3 2051.89  5008.6 2051.39  5012.1 2051.39
  5012.3 2051.89  5041.2 2054.74  5051.5  2057.7  5064.4 2062.62  5072.2 2064.75
  5100.5 2070.14  5105.7 2070.15  5123.7 2073.24  5146.9 2076.19  5175.2  2084.9
    5183 2088.01  5188.1 2088.44  5195.8 2091.33  5203.6 2093.04  5206.2 2093.04
#Mann= 4 ,-1 , 0
  4717.2     .07       0  4886.1      .1       0  5008.3     .05       0
  5012.3      .1       0
Bank Sta=5008.3,5012.3
XS Rating Curve= 0 ,0
Exp/Cntr=0.3,0.1

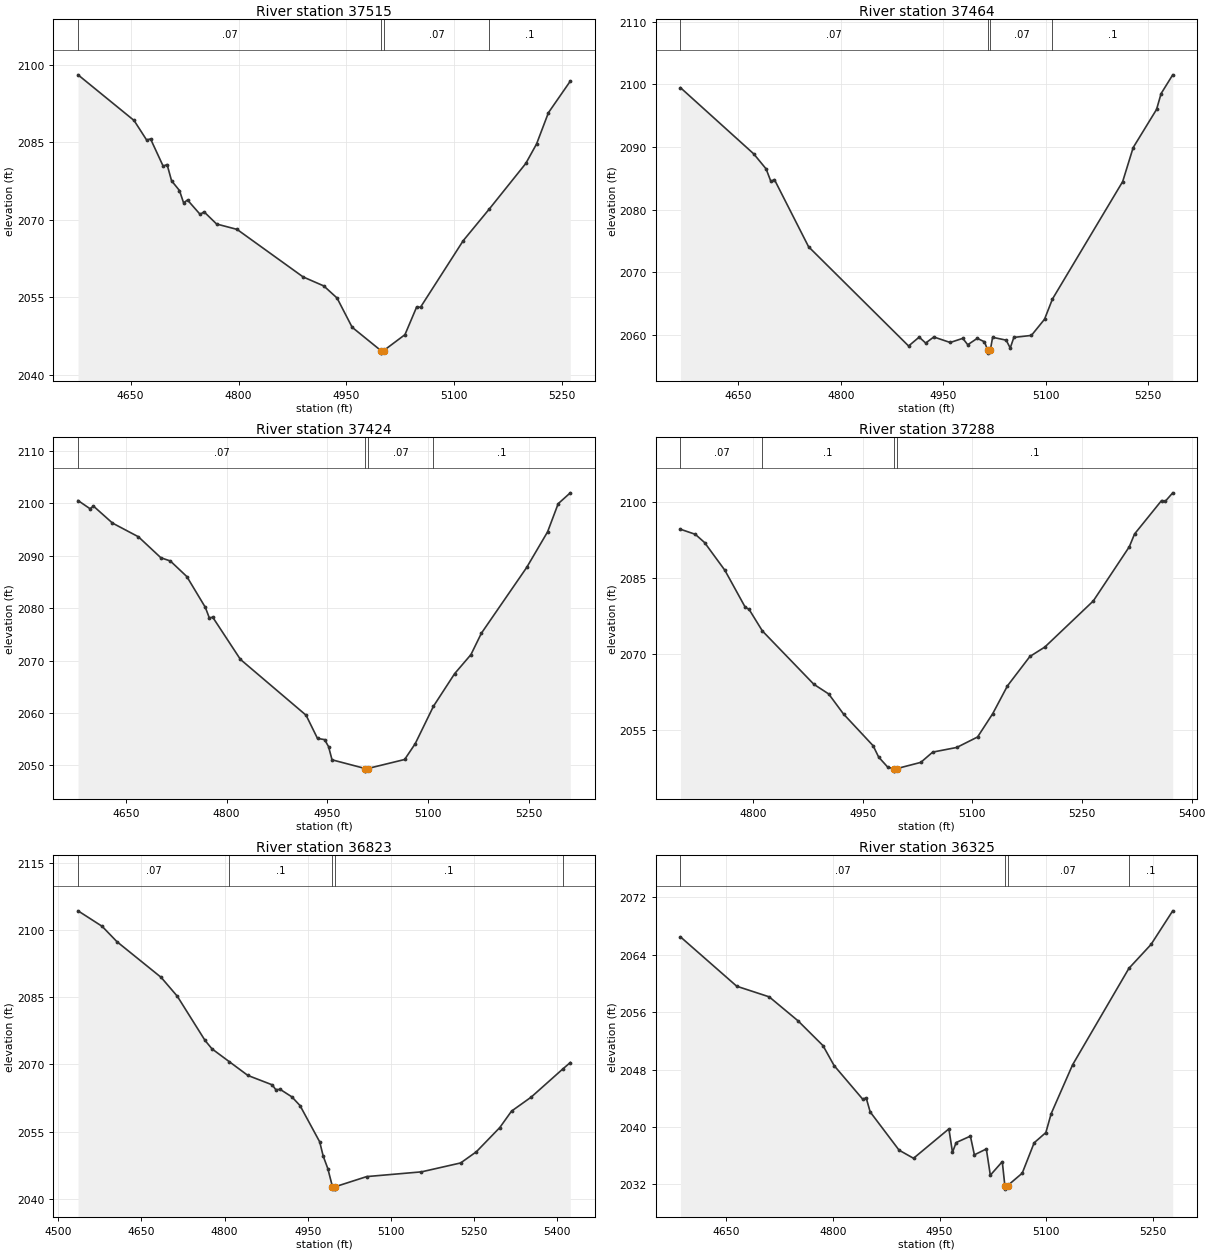
Type RM Length L Ch R = 1 ,37515   ,51,51,51
BEGIN DESCRIPTION:
Tegner Creek 75.3
END DESCRIPTION:
XS GIS Cut Line= 3
        1862587.     13913018.41      1862890.78     13913158.65
      1863224.02     13913264.38
#Sta/Elev= 30
  4576.9  2098.1  4654.8 2089.25  4672.2 2085.48  4677.7 2085.68  4695.2 2080.41
  4700.7 2080.71  4706.9 2077.57  4717.9 2075.68  4723.6  2073.3  4729.1 2073.84
  4746.6 2071.06  4752.1 2071.55  4769.5 2069.19  4797.9 2068.15  4889.7 2058.94
  4918.5 2057.19  4936.9 2054.85  4957.9 2049.18  4997.8 2044.67  4998.1 2044.17
  5001.8 2044.67  5031.3 2047.75  5047.6 2053.13  5052.9 2053.06  5112.2 2065.95
  5148.7 2072.13  5199.2 2080.92  5214.2  2084.7  5230.7 2090.76  5261.1 2096.88
#Mann= 4 ,-1 , 0
  4576.9     .07       0  4997.8     .05       0  5001.8     .07       0
  5148.7      .1       0
Bank Sta=4997.8,5001.8
XS Rating Curve= 0 ,0
Exp/Cntr=0.3,0.1

Type RM Length L Ch R = 1 ,37464   ,40,40,40
BEGIN DESCRIPTION:
Tegner Creek 75.2
END DESCRIPTION:
XS GIS Cut Line= 4
      1862557.44     13913083.29      1862914.32     13913216.21
      1863056.03     13913265.69      1863241.62     13913305.29
#Sta/Elev= 30
  4565.4 2099.49  4672.7 2088.91  4690.8 2086.51  4697.7 2084.53    4703  2084.8
    4753 2074.07  4899.4 2058.22  4914.9 2059.64  4924.4 2058.69  4936.3 2059.66
  4960.3 2058.78  4978.7 2059.44    4986 2058.42  4999.9 2059.44  5010.5 2058.89
  5015.1 2057.58  5015.4 2057.08  5019.1 2057.58  5022.4 2059.61  5042.3 2059.15
  5048.2 2057.89  5053.5 2059.59  5079.2 2059.91  5098.4 2062.49    5110 2065.72
  5212.8 2084.48  5228.2 2089.92  5262.4 2096.01  5269.1 2098.55  5286.1 2101.54
#Mann= 4 ,-1 , 0
  4565.4     .07       0  5015.1     .05       0  5019.1     .07       0
    5110      .1       0
Bank Sta=5015.1,5019.1
XS Rating Curve= 0 ,0
Exp/Cntr=0.3,0.1

Type RM Length L Ch R = 1 ,37424   ,136,136,136
BEGIN DESCRIPTION:
Tegner Creek 75.1
END DESCRIPTION:
XS GIS Cut Line= 3
      1862533.24     13913144.91      1862920.61      13913258.5
      1863237.64     13913344.62
#Sta/Elev= 30
    4579 2100.55  4596.8 2098.99    4602 2099.48  4630.2 2096.25  4668.8 2093.63
  4702.2 2089.63  4716.3 2089.01  4740.8 2086.04  4768.4 2080.15  4774.2 2078.17
  4779.4 2078.27  4820.5 2070.23  4918.2 2059.57  4935.2 2055.14  4945.6 2054.92
  4951.6 2053.59  4956.8 2051.06    5006  2049.4  5006.2  2048.9    5010  2049.4
  5064.8 2051.12  5080.5 2054.13  5107.7 2061.29  5139.2 2067.51  5163.4 2071.14
    5179 2075.23  5246.3 2087.77  5277.4 2094.57  5293.2 2099.95  5311.2 2102.02
#Mann= 4 ,-1 , 0
    4579     .07       0    5006     .05       0    5010     .07       0
  5107.7      .1       0
Bank Sta=5006,5010
XS Rating Curve= 0 ,0
Exp/Cntr=0.3,0.1

Type RM Length L Ch R = 1 ,37288   ,465,465,465
BEGIN DESCRIPTION:
Tegner Creek 75.0
END DESCRIPTION:
XS GIS Cut Line= 3
      1862574.98       13913325.        1862875.       13913375.
      1863236.02     13913452.98
#Sta/Elev= 30
  4700.6 2094.65  4720.9 2093.65  4733.6 2092.02  4761.4 2086.53  4789.3 2079.21
  4794.4 2078.83  4812.7 2074.54  4883.1    2064  4903.4 2062.09  4923.7 2058.12
  4964.2 2051.85  4971.8  2049.6  4984.5 2047.57  4992.6 2047.33  4992.9 2046.83
  4996.6 2047.33  5029.4 2048.56  5045.7 2050.59  5078.6 2051.51  5107.1 2053.58
  5127.9 2058.21    5148 2063.69  5178.7  2069.5  5199.1 2071.36  5265.4 2080.47
  5314.7 2091.19  5321.9 2093.72  5358.8 2100.32    5364 2100.19  5374.1 2101.85
#Mann= 4 ,-1 , 0
  4700.6     .07       0  4812.7      .1       0  4992.6     .05       0
  4996.6      .1       0
Bank Sta=4992.6,4996.6
XS Rating Curve= 0 ,0
Exp/Cntr=0.3,0.1

Type RM Length L Ch R = 1 ,36823   ,498,498,498
BEGIN DESCRIPTION:
Tegner Creek 74.0
END DESCRIPTION:
XS GIS Cut Line= 3
       1862400.8     13913399.92        1862675.       13913775.
      1862975.01     13914075.01
#Sta/Elev= 30
  4535.4 2104.33  4578.8 2100.88  4605.8 2097.42  4685.4 2089.47  4714.7 2085.24
  4764.7 2075.38  4777.3 2073.49  4808.7 2070.61  4842.1 2067.55  4886.1 2065.45
  4892.3  2064.4  4900.8 2064.41  4921.6 2062.76  4936.3 2060.81  4971.8 2052.71
    4978 2049.57  4986.5 2046.72  4994.9 2042.65  4995.2 2042.15  4998.7 2042.15
  4998.9 2042.65  5056.6 2044.95  5155.6 2046.01  5226.3    2048  5254.6 2050.49
    5297 2055.91  5318.2 2059.58  5353.6  2062.7  5410.6 2068.98  5424.3 2070.44
#Mann= 5 ,-1 , 0
  4535.4     .07       0  4808.7      .1       0  4994.9     .05       0
  4998.9      .1       0  5410.6     .07       0
Bank Sta=4994.9,4998.9
XS Rating Curve= 0 ,0
Exp/Cntr=0.3,0.1

Type RM Length L Ch R = 1 ,36325   ,38,38,38
BEGIN DESCRIPTION:
Tegner Creek 73.2
END DESCRIPTION:
XS GIS Cut Line= 4
      1862272.04     13914253.09      1862658.12      13914188.3
      1862765.02      13914135.1      1862945.37     13914122.14
#Sta/Elev= 30
    4586 2066.51  4665.1 2059.63  4710.7 2058.15  4751.2 2054.81  4786.3 2051.35
  4801.9 2048.57  4841.9 2043.91    4847 2044.05  4852.6 2042.11  4893.2 2036.78
  4913.5 2035.65  4963.2 2039.75  4968.2 2036.48  4973.4 2037.84  4993.4 2038.74
    4999 2036.13  5015.8 2036.95  5021.4 2033.29  5038.2 2035.18  5041.8 2031.85
    5042 2031.35  5045.8 2031.85  5066.2 2033.57    5083 2037.81  5099.4 2039.23
  5106.9 2041.87    5137 2048.68  5216.1 2062.12  5247.2 2065.45  5277.7 2070.14
#Mann= 4 ,-1 , 0
    4586     .07       0  5041.8     .05       0  5045.8     .07       0
  5216.1      .1       0
Bank Sta=5041.8,5045.8
XS Rating Curve= 0 ,0
Exp/Cntr=0.3,0.1

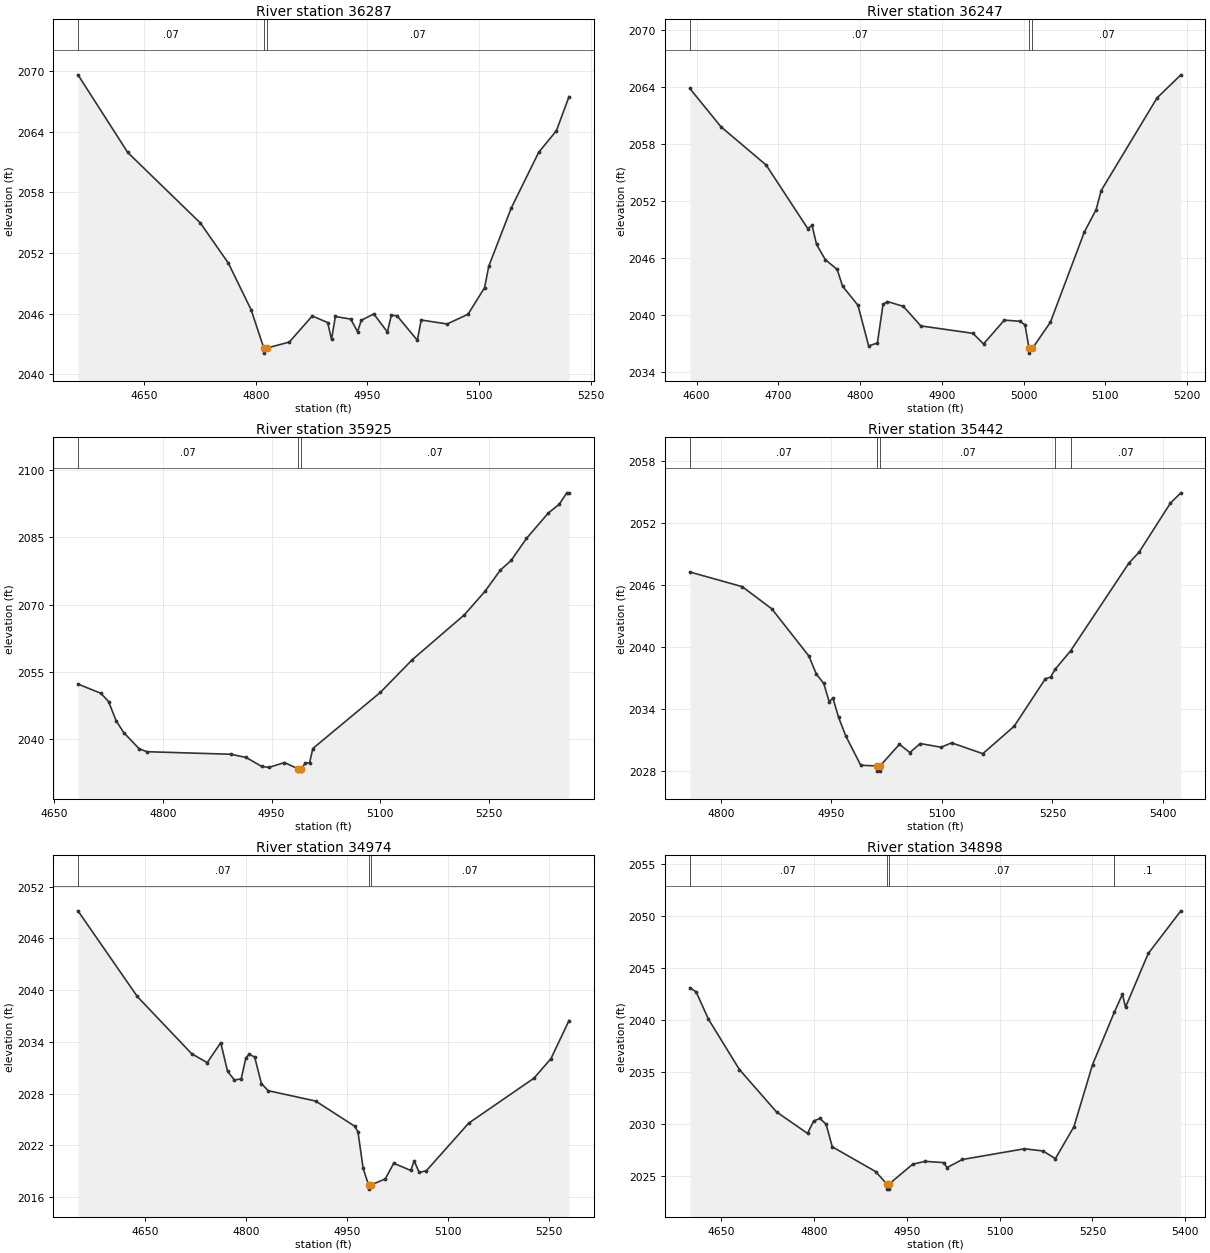
Type RM Length L Ch R = 1 ,36287   ,40,40,40
BEGIN DESCRIPTION:
Tegner Creek 73.1
END DESCRIPTION:
XS GIS Cut Line= 4
      1862277.79     13914305.14       1862572.9     13914239.88
      1862787.32     13914182.89      1862921.79     13914164.74
#Sta/Elev= 30
  4561.1  2069.6    4628 2061.93  4725.5 2054.97  4763.1 2051.01  4793.8 2046.39
  4810.8 2042.61  4811.1 2042.11  4814.8 2042.61    4845  2043.2  4875.9 2045.78
  4896.6 2045.13  4901.8 2043.47    4907 2045.73  4927.6 2045.47  4936.8 2044.23
  4941.9 2045.36  4958.6 2045.98  4976.9  2044.2  4982.1 2045.84  4989.7 2045.81
  5017.1 2043.38  5022.3 2045.38  5057.2 2044.99  5085.2 2045.95  5107.5 2048.58
  5113.1  2050.7  5143.4 2056.46  5180.2 2061.95    5204 2064.08  5220.9 2067.45
#Mann= 3 ,-1 , 0
  4561.1     .07       0  4810.8     .05       0  4814.8     .07       0
Bank Sta=4810.8,4814.8
XS Rating Curve= 0 ,0
Exp/Cntr=0.3,0.1

Type RM Length L Ch R = 1 ,36247   ,322,322,322
BEGIN DESCRIPTION:
Tegner Creek 73.0
END DESCRIPTION:
XS GIS Cut Line= 3
      1862349.17     13914370.51      1862729.45     13914233.83
      1862919.08      13914182.7
#Sta/Elev= 30
  4591.8 2063.86  4629.9 2059.82  4685.2 2055.78    4736 2049.09  4741.3 2049.41
  4746.8 2047.41  4757.4 2045.82    4772 2044.77  4778.6 2043.01  4797.4    2041
  4810.5 2036.71  4821.2 2037.02  4828.1 2041.11  4833.5 2041.39    4853 2040.88
  4874.3 2038.82    4938 2038.04    4951 2036.92  4976.4 2039.43  4995.9 2039.31
  5001.7 2038.91  5006.7 2036.45    5007 2035.95  5010.7 2036.45  5032.7  2039.2
  5074.2 2048.71  5088.6 2051.07  5094.9  2053.1  5163.2 2062.87  5192.3  2065.3
#Mann= 3 ,-1 , 0
  4591.8     .07       0  5006.7     .05       0  5010.7     .07       0
Bank Sta=5006.7,5010.7
XS Rating Curve= 0 ,0
Exp/Cntr=0.3,0.1

Type RM Length L Ch R = 1 ,35925   ,483,483,483
BEGIN DESCRIPTION:
Tegner Creek 72.0
END DESCRIPTION:
XS GIS Cut Line= 3
      1862525.01       13914625.        1862825.       13914525.
      1863125.02     13914324.99
#Sta/Elev= 30
  4683.2 2052.26  4714.8 2050.19  4725.4 2048.34  4735.9 2044.03  4746.4 2041.38
  4767.5 2037.81  4778.1 2037.14    4894 2036.57  4915.1 2035.85  4936.2 2033.86
  4946.7 2033.64  4967.8 2034.72  4986.9  2033.3  4987.1  2032.8  4990.6  2032.8
  4990.9  2033.3  4996.8 2034.63  5002.4 2034.63  5006.9 2037.85  5100.1 2050.41
  5143.6 2057.64  5215.8 2067.73  5244.3 2072.99  5265.3  2077.7  5280.4  2079.9
  5301.4 2084.79  5331.4 2090.45  5346.5 2092.42    5357 2094.98    5360 2094.98
#Mann= 3 ,-1 , 0
  4683.2     .07       0  4986.9     .05       0  4990.9     .07       0
Bank Sta=4986.9,4990.9
XS Rating Curve= 0 ,0
Exp/Cntr=0.3,0.1

Type RM Length L Ch R = 1 ,35442   ,468,468,468
BEGIN DESCRIPTION:
Tegner Creek 71.0
END DESCRIPTION:
XS GIS Cut Line= 3
      1862584.21     13914951.04        1862825.       13914975.
      1863124.97     13914675.03
#Sta/Elev= 30
  4758.1 2047.25  4829.2 2045.83  4869.4 2043.68  4919.7 2039.11  4929.7 2037.38
  4939.8 2036.46  4947.2 2034.69  4952.2 2035.06  4959.9 2033.19  4969.9 2031.35
    4990 2028.55  5012.2 2028.48  5012.5 2027.98    5016 2027.98  5016.2 2028.48
  5042.5 2030.58  5056.6 2029.78  5070.8 2030.65  5099.1 2030.29  5113.2 2030.72
  5155.6 2029.67  5198.1 2032.32  5240.5 2036.92  5247.6 2037.08  5253.9 2037.85
  5274.6 2039.61  5353.6 2048.09  5367.8 2049.19  5410.2 2053.92  5424.3 2054.91
#Mann= 5 ,-1 , 0
  4758.1     .07       0  5012.2     .05       0  5016.2     .07       0
  5253.9      .1       0  5274.6     .07       0
Bank Sta=5012.2,5016.2
XS Rating Curve= 0 ,0
Exp/Cntr=0.3,0.1

Type RM Length L Ch R = 1 ,34974   ,76,76,76
BEGIN DESCRIPTION:
Tegner Creek 70.0
END DESCRIPTION:
XS GIS Cut Line= 3
      1862574.29     13915431.14        1863025.       13915375.
      1863284.19     13915280.43
#Sta/Elev= 30
  4550.1  2049.2  4638.3 2039.27  4719.1 2032.64  4742.3  2031.6  4762.4 2033.92
  4772.5  2030.6  4782.6  2029.6  4792.7 2029.71  4799.9 2032.19  4804.9 2032.56
  4812.8 2032.25  4822.9 2029.17    4833 2028.35  4903.5 2027.15  4961.4 2024.24
  4966.4 2023.59  4974.1 2019.36  4982.1 2017.44  4982.4 2016.94  4986.1 2017.44
    5007 2018.12  5019.6 2019.94  5044.8 2019.11  5050.1  2020.2  5057.5 2018.87
  5068.2 2019.08  5131.1 2024.59  5228.1  2029.8  5253.4 2032.07  5280.2 2036.48
#Mann= 3 ,-1 , 0
  4550.1     .07       0  4982.1     .05       0  4986.1     .07       0
Bank Sta=4982.1,4986.1
XS Rating Curve= 0 ,0
Exp/Cntr=0.3,0.1

Type RM Length L Ch R = 1 ,34898   ,47,47,47
BEGIN DESCRIPTION:
Tegner Creek 69.1
END DESCRIPTION:
XS GIS Cut Line= 4
      1862624.89     13915453.18      1862994.54     13915452.97
      1863172.84      13915441.4      1863417.71     13915439.17
#Sta/Elev= 30
  4599.6 2043.08  4609.7 2042.71  4629.7 2040.07  4679.7 2035.23  4739.7 2031.15
  4789.7 2029.09  4799.7 2030.28  4809.7 2030.53  4819.7 2029.97  4829.7  2027.8
  4899.7 2025.42  4917.7 2024.23    4918 2023.73  4921.5 2023.73  4921.7 2024.23
  4959.7 2026.13  4979.7  2026.4  5009.8 2026.28    5015  2025.8  5039.9 2026.58
  5140.1 2027.61  5170.1  2027.4  5190.1 2026.66  5220.1 2029.74  5250.1 2035.69
  5285.2 2040.73  5298.4 2042.47  5303.4 2041.23  5340.1 2046.39  5392.8 2050.49
#Mann= 4 ,-1 , 0
  4599.6     .07       0  4917.7     .05       0  4921.7     .07       0
  5285.2      .1       0
Bank Sta=4917.7,4921.7
XS Rating Curve= 0 ,0
Exp/Cntr=0.3,0.1

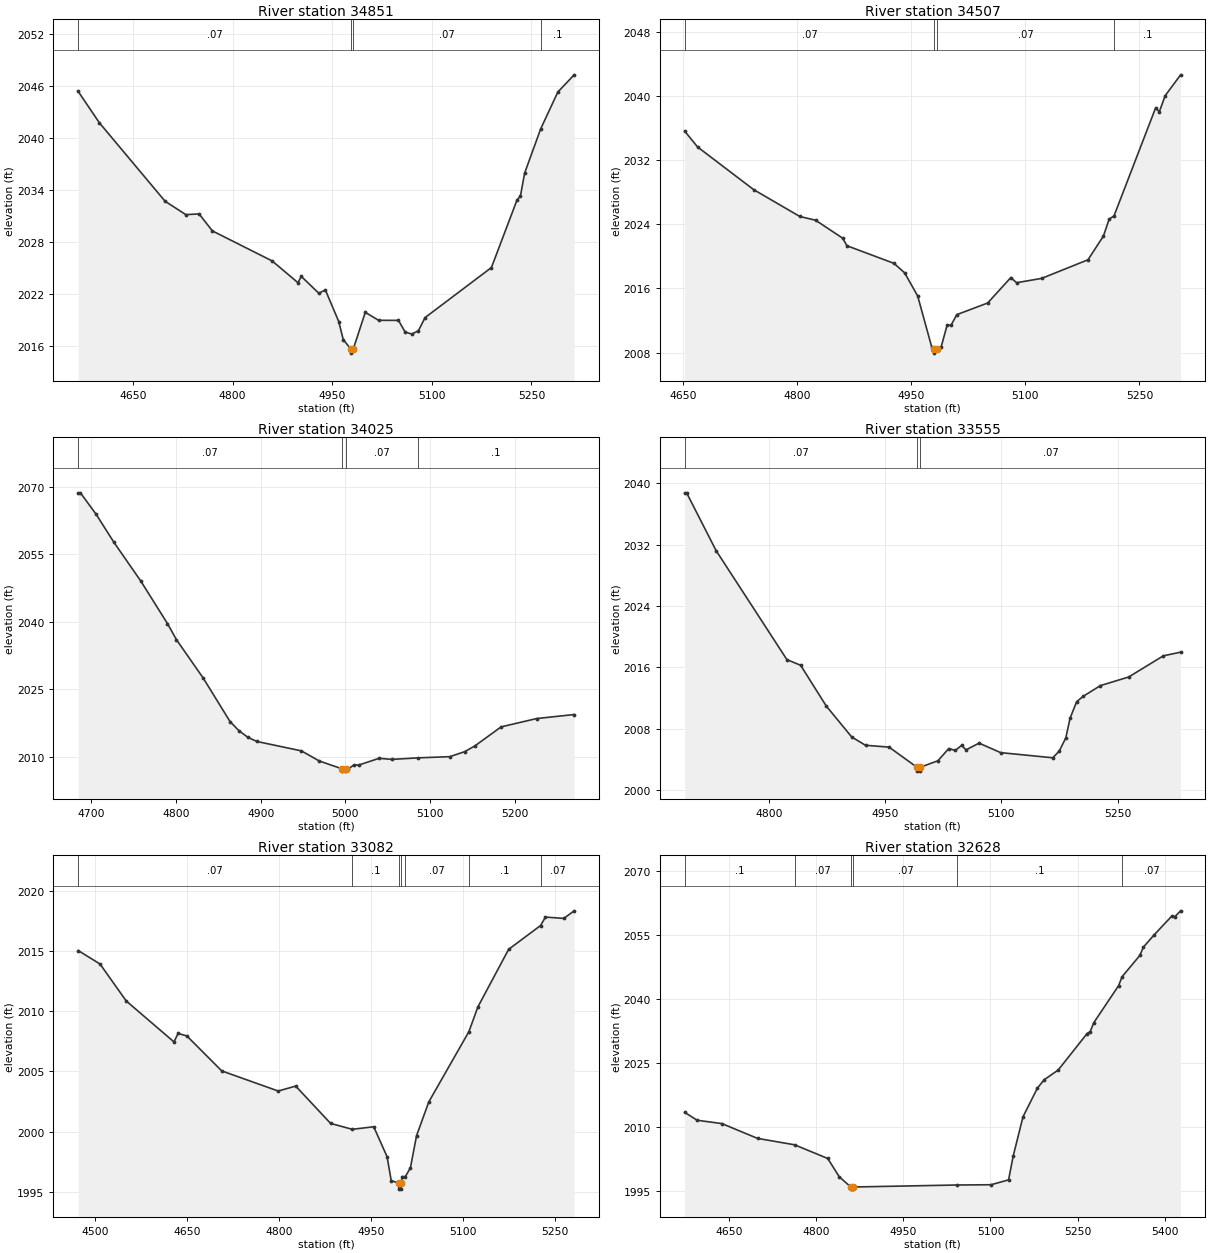
Type RM Length L Ch R = 1 ,34851   ,344,344,344
BEGIN DESCRIPTION:
Tegner Creek 69.2
END DESCRIPTION:
XS GIS Cut Line= 3
      1862593.12     13915516.75      1862993.69     13915496.68
      1863339.59     13915501.04
#Sta/Elev= 30
  4567.4  2045.4  4599.3 2041.78  4698.3 2032.72  4729.5 2031.18  4749.5 2031.26
  4769.5  2029.3  4859.6 2025.83  4898.4 2023.32  4903.4 2024.05  4929.7 2022.11
  4939.7 2022.48  4959.8 2018.84  4966.6 2016.75  4977.8 2015.69    4978 2015.19
  4981.8 2015.69  4999.8  2019.9  5019.8 2018.98  5049.8 2018.97  5059.8 2017.63
  5069.8 2017.39  5079.8 2017.77  5089.8 2019.29  5189.8 2025.07  5228.4 2032.88
  5233.4 2033.29  5239.8 2035.97    5264 2041.08  5289.8 2045.33  5314.4 2047.32
#Mann= 4 ,-1 , 0
  4567.4     .07       0  4977.8     .05       0  4981.8     .07       0
    5264      .1       0
Bank Sta=4977.8,4981.8
XS Rating Curve= 0 ,0
Exp/Cntr=0.3,0.1

Type RM Length L Ch R = 1 ,34507   ,482,482,482
BEGIN DESCRIPTION:
Tegner Creek 69.0
END DESCRIPTION:
XS GIS Cut Line= 3
      1862638.56     13915738.35        1862975.       13915825.
      1863275.04     13915774.99
#Sta/Elev= 30
  4652.5 2035.62  4669.5 2033.64  4743.1 2028.33  4803.7 2024.98  4824.5 2024.51
  4860.1 2022.27  4865.7 2021.33  4927.6 2019.13  4941.5 2017.95  4958.6 2015.07
    4977 2008.73  4980.2 2008.44  4980.4 2007.94  4984.2 2008.44  4989.6 2008.75
  4997.3 2011.43  5002.5 2011.43  5010.1 2012.74  5050.6 2014.19    5081 2017.36
  5088.6 2016.72  5121.6 2017.26  5182.4 2019.58  5202.7 2022.54  5210.3 2024.67
  5216.5 2025.03  5271.1 2038.48  5276.2 2038.05  5283.8 2040.04  5304.1 2042.64
#Mann= 4 ,-1 , 0
  4652.5     .07       0  4980.2     .05       0  4984.2     .07       0
  5216.5      .1       0
Bank Sta=4980.2,4984.2
XS Rating Curve= 0 ,0
Exp/Cntr=0.3,0.1

Type RM Length L Ch R = 1 ,34025   ,470,470,470
BEGIN DESCRIPTION:
Tegner Creek 68.0
END DESCRIPTION:
XS GIS Cut Line= 3
        1862575.       13916375.        1862875.       13916275.
      1863125.02     13916174.99
#Sta/Elev= 30
  4684.6 2068.66  4687.2 2068.66  4705.7 2063.91  4726.8 2057.66  4758.4 2049.09
    4790 2039.62  4800.5 2036.07  4832.2 2027.52  4863.8 2017.88  4874.3 2015.84
  4884.9 2014.37  4895.4 2013.45  4948.1 2011.36  4969.2 2009.11  4996.2 2007.36
  4996.4 2006.86  4999.9 2006.86  5000.2 2007.36  5003.5 2007.36  5010.2 2008.25
  5015.6  2008.2  5039.9 2009.71  5054.7 2009.46  5085.9 2009.81  5123.3 2010.07
  5140.8 2011.18    5153 2012.47  5183.9 2016.69  5225.7 2018.53  5270.1 2019.43
#Mann= 4 ,-1 , 0
  4684.6     .07       0  4996.2     .05       0  5000.2     .07       0
  5085.9      .1       0
Bank Sta=4996.2,5000.2
XS Rating Curve= 0 ,0
Exp/Cntr=0.3,0.1

Type RM Length L Ch R = 1 ,33555   ,473,473,473
BEGIN DESCRIPTION:
Tegner Creek 67.0
END DESCRIPTION:
XS GIS Cut Line= 3
      1862775.01       13916725.        1863075.       13916675.
      1863224.98     13916375.04
#Sta/Elev= 30
  4691.6 2038.74  4694.1 2038.74  4732.1 2031.21  4823.4    2017  4841.1 2016.26
  4874.1 2010.96    4907 2006.91  4924.8 2005.83  4955.2 2005.59  4991.2 2002.96
  4991.4 2002.46  4994.9 2002.46  4995.2 2002.96  5018.1 2003.81  5032.1  2005.4
  5040.5 2005.16  5048.8 2005.82  5054.4 2005.23  5071.2 2006.11  5099.1 2004.87
  5166.2  2004.2  5174.6 2005.07    5183 2006.78  5188.6 2009.37    5197  2011.5
  5205.4 2012.21  5227.7 2013.61  5264.1 2014.73  5308.8 2017.49  5331.1 2017.97
#Mann= 3 ,-1 , 0
  4691.6     .07       0  4991.2     .05       0  4995.2     .07       0
Bank Sta=4991.2,4995.2
XS Rating Curve= 0 ,0
Exp/Cntr=0.3,0.1

Type RM Length L Ch R = 1 ,33082   ,454,454,454
BEGIN DESCRIPTION:
Tegner Creek 66.0
END DESCRIPTION:
XS GIS Cut Line= 3
        1863125.       13917025.        1863525.       13916675.
      1863516.08     13916398.25
#Sta/Elev= 30
  4472.9 2015.04  4508.5 2013.92  4551.2 2010.85    4629 2007.45  4635.7 2008.15
  4649.9 2007.95  4706.9 2005.04  4798.9 2003.37  4827.4 2003.78  4884.3 2000.68
  4919.5 2000.19  4954.6  2000.4  4976.4 1997.91  4983.1 1995.93  4995.2 1995.72
  4995.5 1995.22  4999.1 1995.22  4999.4 1995.72  5001.1 1996.26  5006.1 1996.26
  5014.4 1996.99  5024.4 1999.66  5044.4 2002.47  5109.7  2008.3  5124.5 2010.37
  5174.5 2015.14  5226.6 2017.12  5234.5 2017.82  5264.5 2017.71  5281.3 2018.34
#Mann= 7 ,-1 , 0
  4472.9     .07       0  4919.5      .1       0  4995.2     .05       0
  4999.4      .1       0  5006.1     .07       0  5109.7      .1       0
  5226.6     .07       0
Bank Sta=4995.2,4999.4
XS Rating Curve= 0 ,0
Exp/Cntr=0.3,0.1

Type RM Length L Ch R = 1 ,32628   ,456,456,456
BEGIN DESCRIPTION:
Tegner Creek 65.0
END DESCRIPTION:
XS GIS Cut Line= 3
      1863225.02     13917174.99        1863625.       13917025.
      1864025.02     13916874.99
#Sta/Elev= 30
  4573.2 2013.37  4594.5 2011.51  4637.3 2010.72  4698.7 2007.25  4762.6 2005.74
  4819.7 2002.53  4839.3 1998.28  4859.3 1995.84  4859.6 1995.34  4863.5 1995.34
  4863.8 1995.84    5043 1996.31  5100.9 1996.37  5131.2 1997.51  5139.2 2003.12
  5156.1 2012.33    5181 2019.08  5192.6 2021.01  5216.6 2023.28  5266.5 2031.85
  5271.8  2032.3  5278.1 2034.42  5320.8  2043.1  5326.8  2045.2  5357.3 2050.17
  5363.5 2052.14  5382.2 2055.04  5412.4 2059.42  5417.8  2059.3  5427.6 2060.65
#Mann= 6 ,-1 , 0
  4573.2      .1       0  4762.6     .07       0  4859.3     .05       0
  4863.8     .07       0    5043      .1       0  5326.8     .07       0
Bank Sta=4859.3,4863.8
XS Rating Curve= 0 ,0
Exp/Cntr=0.3,0.1

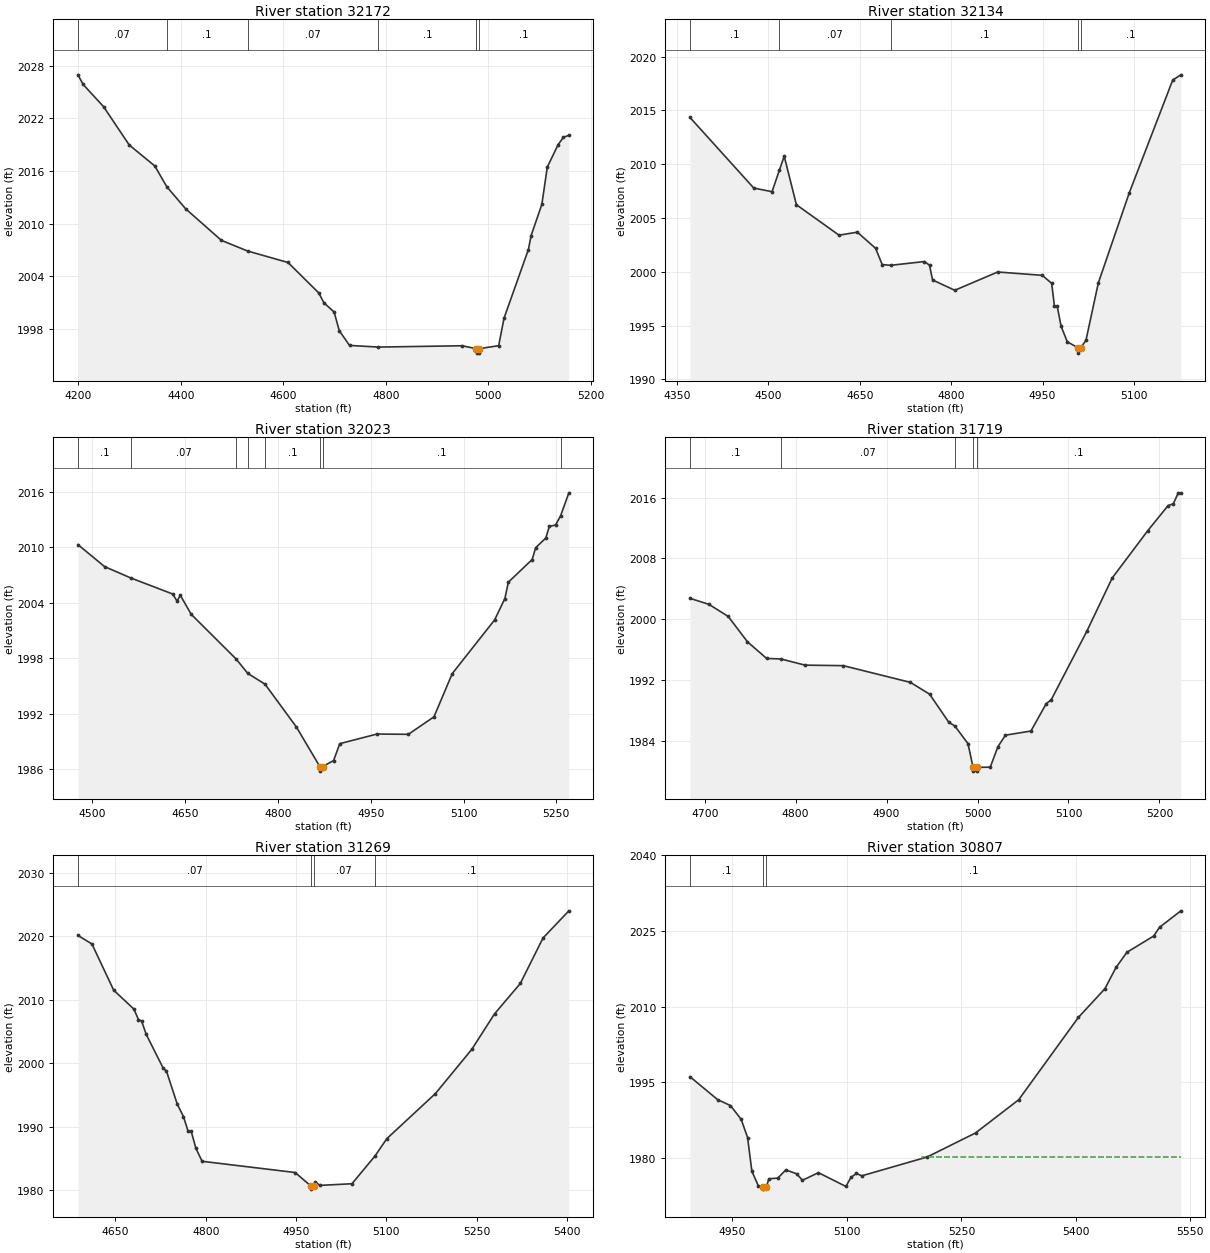
Type RM Length L Ch R = 1 ,32172   ,38,38,38
BEGIN DESCRIPTION:
Tegner Creek 64.0
END DESCRIPTION:
XS GIS Cut Line= 3
        1863025.       13917375.        1863825.       13917375.
      1863974.98     13917325.01
#Sta/Elev= 30
  4199.1 2026.97  4209.1 2025.88  4249.1 2023.34  4299.1 2018.98  4349.1 2016.58
  4372.2 2014.24  4409.1 2011.71  4479.1  2008.1  4530.1 2006.89  4609.1 2005.58
  4669.1 2002.11  4679.1 2000.99  4699.1 1999.93  4709.1 1997.81  4729.1 1996.13
  4785.4 1995.94  4949.1 1996.09  4976.9 1995.75  4977.2 1995.25  4981.1 1995.25
  4981.4 1995.75  5020.2  1996.1  5030.7 1999.24  5078.2 2007.05  5083.4 2008.62
  5104.5 2012.21  5115.1 2016.45  5136.1    2019  5146.7 2019.86  5157.2 2020.07
#Mann= 6 ,-1 , 0
  4199.1     .07       0  4372.2      .1       0  4530.1     .07       0
  4785.4      .1       0  4976.9     .05       0  4981.4      .1       0
Bank Sta=4976.9,4981.4
XS Rating Curve= 0 ,0
Exp/Cntr=0.3,0.1

Type RM Length L Ch R = 1 ,32134   ,111,111,111
BEGIN DESCRIPTION:
Mapping XS c6795235
END DESCRIPTION:
XS GIS Cut Line= 5
      1863200.35     13917443.84      1863554.01     13917450.84
      1863694.47     13917448.09      1863798.65     13917417.41
      1863998.21     13917380.28
#Sta/Elev= 30
  4371.2 2014.34  4475.9 2007.78  4505.9 2007.44  4517.9 2009.42  4525.9 2010.74
  4545.9 2006.23  4615.9  2003.4  4645.9 2003.68  4675.9 2002.18  4686.7 2000.67
  4700.8  2000.6  4755.9 2000.95  4764.4 2000.61  4769.4 1999.24  4805.9 1998.28
  4876.4 1999.98  4949.4 1999.67  4964.9 1998.93  4969.5 1996.79    4974 1996.79
  4980.5 1994.92  4990.6 1993.49    5008 1992.94  5008.3 1992.44  5012.5 1992.94
  5021.2 1993.63  5041.5 1998.96  5092.4 2007.35  5163.6 2017.81    5177  2018.3
#Mann= 5 ,-1 , 0
  4371.2      .1       0  4517.9     .07       0  4700.8      .1       0
    5008     .05       0  5012.5      .1       0
Bank Sta=5008,5012.5
XS Rating Curve= 0 ,0
Exp/Cntr=0.3,0.1

Type RM Length L Ch R = 1 ,32023   ,304,304,304
BEGIN DESCRIPTION:
Mapping XS b0dc541a
END DESCRIPTION:
XS GIS Cut Line= 4
      1863251.95     13917522.13       1863728.8     13917515.88
      1863876.31     13917490.62      1864024.08     13917413.35
#Sta/Elev= 30
  4476.9 2010.27    4520 2007.89  4562.8 2006.65    4630 2004.93  4637.2 2004.15
  4642.2  2004.8    4660 2002.73  4732.4 1997.91  4751.3 1996.35  4779.2 1995.18
    4830 1990.54  4867.7 1986.28    4868 1985.78  4872.3 1986.28    4890 1986.92
    4900 1988.75  4960.1 1989.79  5010.8 1989.76  5052.2 1991.65  5081.8 1996.33
  5150.3 2002.14  5166.8 2004.44  5172.4 2006.21  5210.9 2008.66  5216.6 2009.94
    5233 2010.99  5238.6 2012.24  5248.7 2012.39  5256.8 2013.38  5270.2 2015.87
#Mann= 8 ,-1 , 0
  4476.9      .1       0  4562.8     .07       0  4732.4      .1       0
  4751.3     .07       0  4779.2      .1       0  4867.7     .05       0
  4872.3      .1       0  5256.8     .07       0
Bank Sta=4867.7,4872.3
XS Rating Curve= 0 ,0
Exp/Cntr=0.3,0.1

Type RM Length L Ch R = 1 ,31719   ,450,450,450
BEGIN DESCRIPTION:
Tegner Creek 63.0
END DESCRIPTION:
XS GIS Cut Line= 3
      1863375.03     13917675.01        1863675.       13917775.
      1863874.99       13917875.
#Sta/Elev= 30
  4683.8 2002.76  4704.9 2001.95  4725.9 2000.37    4747 1997.04  4768.1 1994.85
  4783.8 1994.78  4810.3 1993.97  4852.4  1993.9  4926.2  1991.7  4947.3 1990.15
  4968.4 1986.46  4975.1 1985.96  4989.5 1983.65  4995.1 1980.53  4995.4 1980.03
  4999.4 1980.03  4999.7 1980.53    5014 1980.55  5022.4 1983.24  5030.7 1984.76
  5058.7  1985.3  5075.5 1988.89  5081.1 1989.43  5120.2 1998.43  5148.1 2005.43
  5187.3 2011.67  5209.6 2014.96  5215.2 2015.18  5220.8 2016.63  5223.6 2016.63
#Mann= 5 ,-1 , 0
  4683.8      .1       0  4783.8     .07       0  4975.1      .1       0
  4995.1     .05       0  4999.7      .1       0
Bank Sta=4995.1,4999.7
XS Rating Curve= 0 ,0
Exp/Cntr=0.3,0.1

Type RM Length L Ch R = 1 ,31269   ,462,462,462
BEGIN DESCRIPTION:
Tegner Creek 62.0
END DESCRIPTION:
XS GIS Cut Line= 3
      1863124.96     13918275.01        1863525.       13918175.
      1863925.03       13918125.
#Sta/Elev= 30
  4587.7 2020.16  4610.9 2018.81    4647 2011.53  4680.5 2008.55  4688.2  2006.9
  4693.4 2006.66  4701.1 2004.55  4729.5 1999.19  4734.6  1998.8  4752.7 1993.54
    4763 1991.59  4770.7 1989.25  4775.9 1989.24  4783.6  1986.6  4793.9 1984.54
  4948.5 1982.77  4974.5 1980.65  4974.9 1980.15  4979.2 1980.65    4982 1981.26
  4989.7 1980.74  5042.9    1981    5081 1985.36  5100.8 1988.11  5181.5 1995.22
  5241.9 2002.19  5279.7 2007.79  5322.5 2012.58  5360.3 2019.76  5403.2 2024.04
#Mann= 4 ,-1 , 0
  4587.7     .07       0  4974.5     .05       0  4979.2     .07       0
    5081      .1       0
Bank Sta=4974.5,4979.2
XS Rating Curve= 0 ,0
Exp/Cntr=0.3,0.1

Type RM Length L Ch R = 1 ,30807   ,455,455,455
BEGIN DESCRIPTION:
Tegner Creek 61.0
END DESCRIPTION:
XS GIS Cut Line= 3
      1863474.99     13918575.01        1863575.       13918525.
      1863974.98     13918175.02
#Sta/Elev= 30
  4894.3 1996.14  4930.6 1991.59  4947.4 1990.42  4961.4 1987.69  4969.8 1984.08
  4975.4 1977.43  4983.8 1974.54  4989.8 1974.36  4990.1 1973.86  4994.5 1974.36
  4997.7 1975.91  5009.4 1976.05  5019.9 1977.66  5034.1  1976.9  5041.7 1975.61
  5062.6 1977.12  5098.7 1974.39  5105.3  1976.2  5112.4 1976.96  5119.5  1976.5
    5205 1980.22  5268.5 1984.99    5325 1991.56  5403.3 2007.89    5438 2013.56
  5452.7 2017.81  5466.9 2020.79    5502 2024.02  5509.6 2025.74  5537.6 2029.01
#Mann= 3 ,-1 , 0
  4894.3      .1       0  4989.8     .05       0  4994.5      .1       0
#XS Ineff= 2 , 0
                            5198         1980.18
Permanent Ineff=
       F       F
Bank Sta=4989.8,4994.5
XS Rating Curve= 0 ,0
Exp/Cntr=0.3,0.1