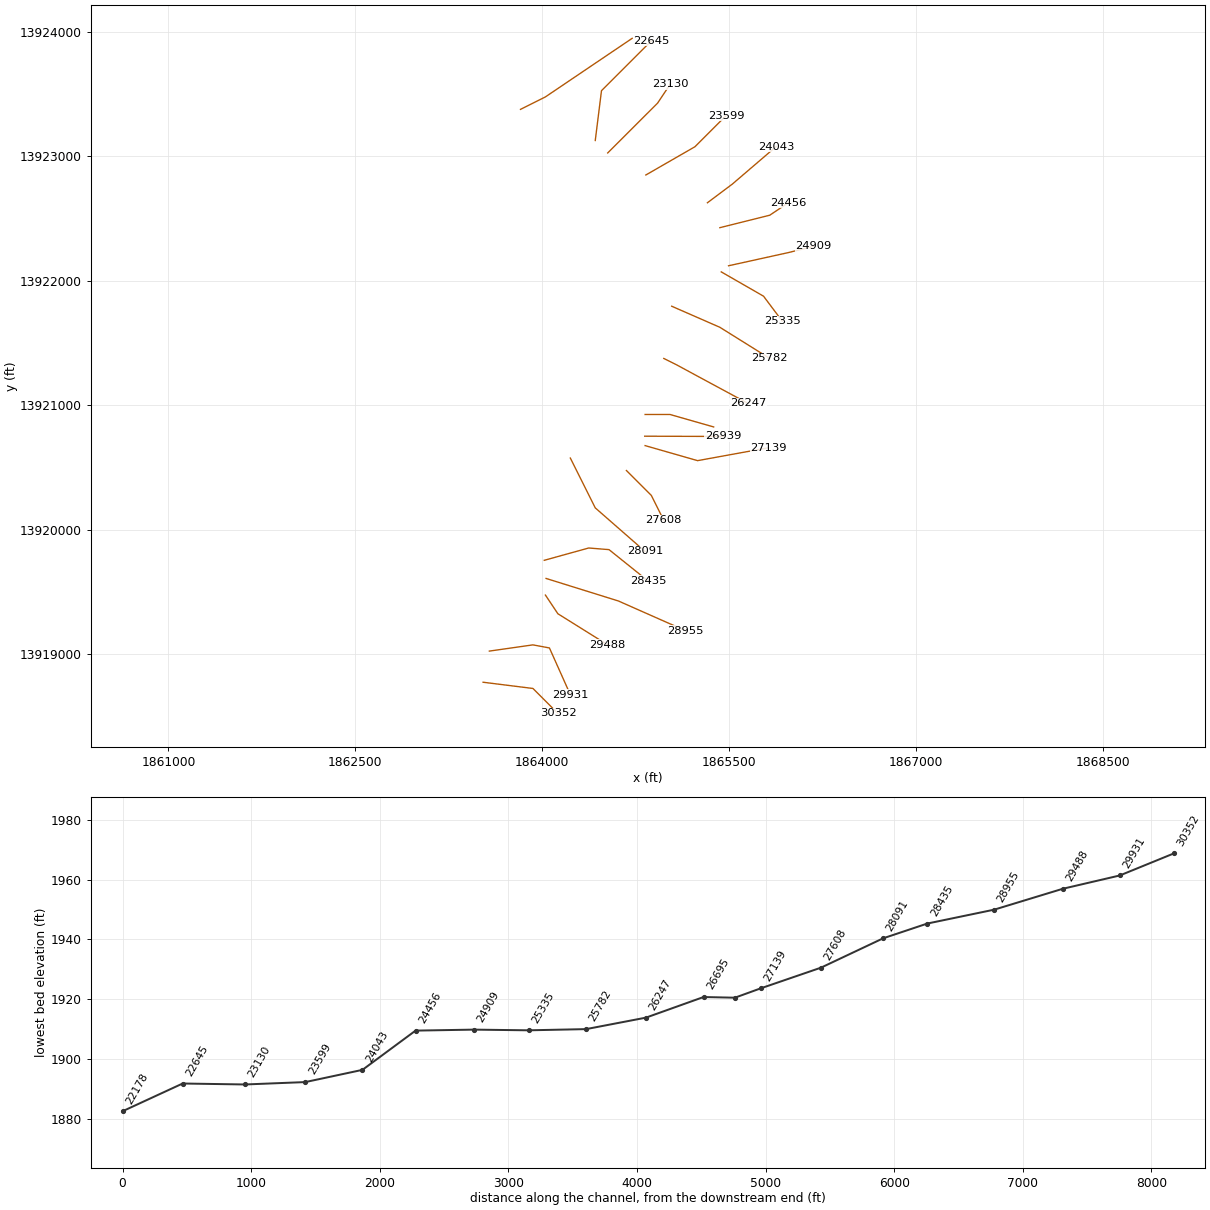
HEC-RAS study Tegener Creek.prj: Tegener Creek Base Level Engineering

--- Tegener Creek.g01 (geometry) --- (continued)

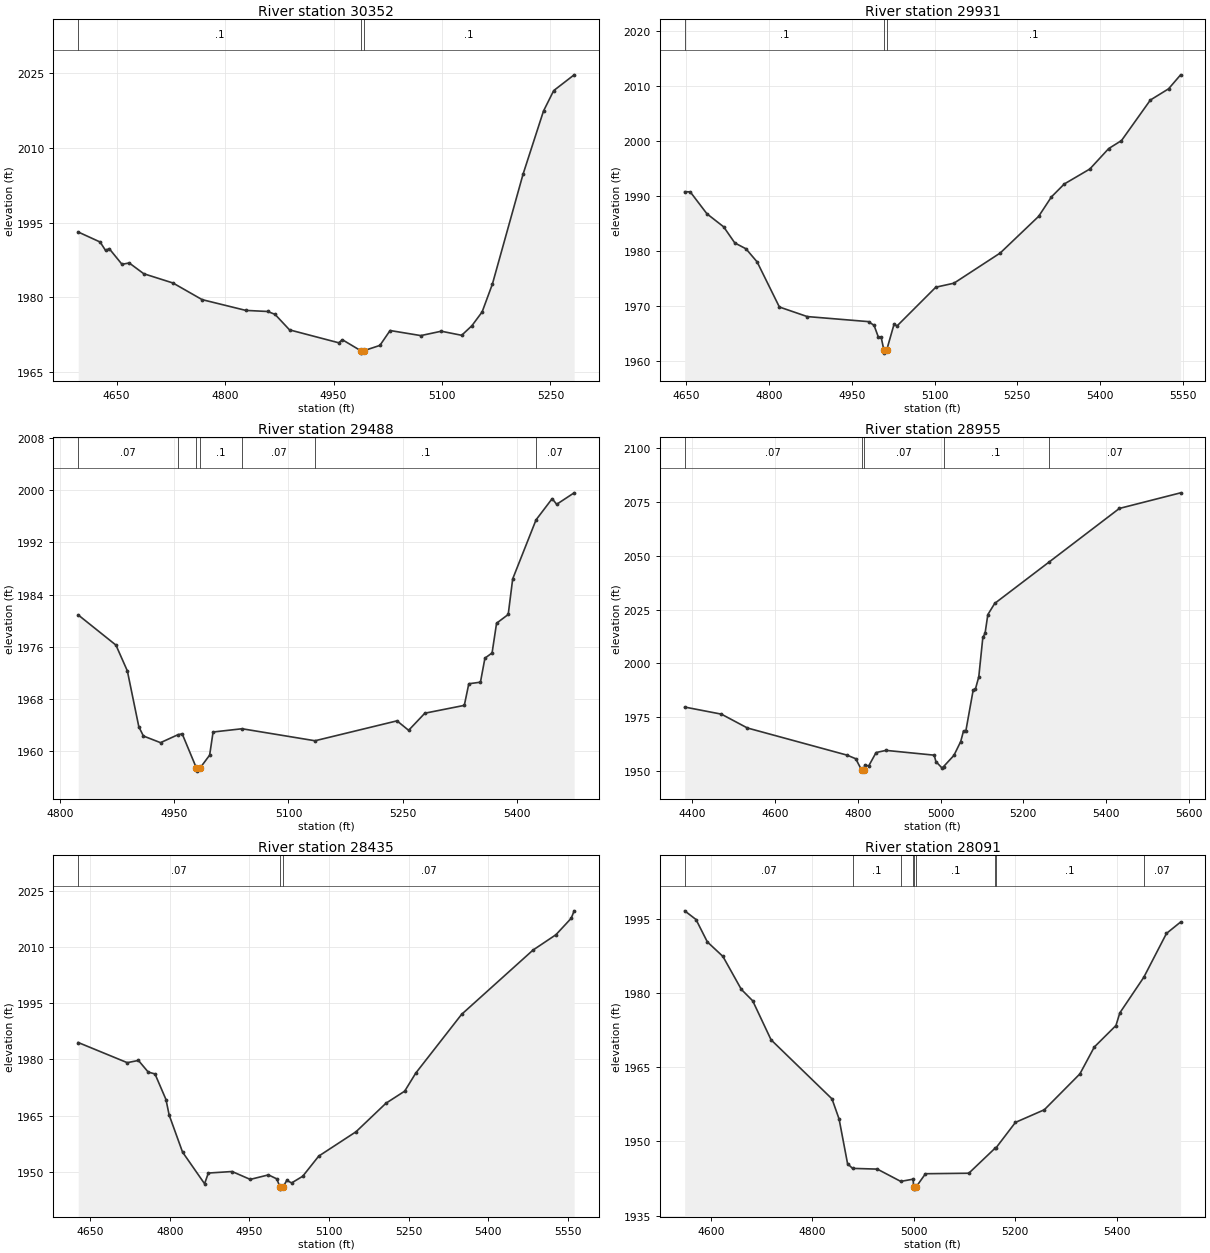
Type RM Length L Ch R = 1 ,30352   ,421,421,421
BEGIN DESCRIPTION:
Tegner Creek 60.0
END DESCRIPTION:
XS GIS Cut Line= 3
      1863524.95     13918775.01        1863925.       13918725.
        1864125.       13918525.
#Sta/Elev= 30
  4596.8 1993.12  4627.1 1991.11  4634.6 1989.42  4639.7 1989.78  4657.3 1986.64
  4667.4  1986.9  4687.5 1984.74  4727.9 1982.88  4768.2 1979.54  4828.6 1977.38
  4858.9 1977.16    4869 1976.59  4889.1 1973.47  4957.1 1970.88  4962.2 1971.49
  4987.5  1969.3  4987.8  1968.8  4992.2  1969.3  5014.1 1970.35  5028.2 1973.34
  5070.7 1972.32    5099  1973.2  5127.2 1972.38  5141.4 1974.31  5155.5 1977.07
  5169.7 1982.66  5212.1 2004.72  5240.4 2017.41  5254.5 2021.51  5282.8 2024.68
#Mann= 3 ,-1 , 0
  4596.8      .1       0  4987.5     .05       0  4992.2      .1       0
Bank Sta=4987.5,4992.2
XS Rating Curve= 0 ,0
Exp/Cntr=0.3,0.1

Type RM Length L Ch R = 1 ,29931   ,443,443,443
BEGIN DESCRIPTION:
Tegner Creek 59.0
END DESCRIPTION:
XS GIS Cut Line= 4
      1863575.04     13919025.01        1863925.       13919075.
      1864057.37     13919050.25      1864225.01     13918674.97
#Sta/Elev= 30
  4646.9 1990.77    4657 1990.74  4687.3 1986.75  4717.6 1984.38  4737.8 1981.45
    4758 1980.39  4778.2 1978.01  4818.6  1969.8  4869.1 1968.06  4980.2 1967.14
  4990.3 1966.46  4997.9 1964.37    5003 1964.37  5008.2 1961.91  5008.5 1961.41
    5013 1961.91  5026.7 1966.73  5031.8 1966.34  5102.2  1973.4  5135.1 1974.13
    5219 1979.62  5288.7 1986.29  5311.9 1989.83  5335.1 1992.17  5381.5  1994.9
  5415.7 1998.62  5438.9 2000.07  5491.3 2007.45  5524.2 2009.48  5546.1 2012.03
#Mann= 3 ,-1 , 0
  4646.9      .1       0  5008.2     .05       0    5013      .1       0
Bank Sta=5008.2,5013
XS Rating Curve= 0 ,0
Exp/Cntr=0.3,0.1

Type RM Length L Ch R = 1 ,29488   ,533,533,533
BEGIN DESCRIPTION:
Tegner Creek 58.0
END DESCRIPTION:
XS GIS Cut Line= 3
      1864024.98     13919475.03        1864125.       13919325.
      1864524.99     13919075.01
#Sta/Elev= 30
  4823.6 1980.88  4873.2 1976.26  4888.2 1972.31  4903.3 1963.75  4909.3 1962.34
  4931.8 1961.32  4954.8 1962.54  4960.3 1962.67  4978.9 1957.46  4979.2 1956.96
  4983.9 1957.46  4996.4 1959.41  5000.9 1962.95    5039 1963.45  5134.9 1961.61
  5242.7 1964.66    5258 1963.21  5279.3 1965.83  5331.2 1967.03  5337.1 1970.34
  5352.4 1970.58  5358.3 1974.26  5367.7 1975.06  5373.6 1979.61  5388.9 1980.95
  5394.8  1986.4  5425.5 1995.44  5446.7 1998.69  5452.6 1997.82  5475.6 1999.58
#Mann= 7 ,-1 , 0
  4823.6     .07       0  4954.8      .1       0  4978.9     .05       0
  4983.9      .1       0    5039     .07       0  5134.9      .1       0
  5425.5     .07       0
Bank Sta=4978.9,4983.9
XS Rating Curve= 0 ,0
Exp/Cntr=0.3,0.1

Type RM Length L Ch R = 1 ,28955   ,520,520,520
BEGIN DESCRIPTION:
Tegner Creek 57.0
END DESCRIPTION:
XS GIS Cut Line= 3
      1864030.25     13919608.41      1864610.29     13919427.57
      1865151.19     13919188.15
#Sta/Elev= 30
  4381.4 1979.72  4470.2 1976.42    4533    1970  4773.9  1957.4  4794.9 1955.73
  4809.2 1950.47  4809.6 1949.97  4814.3 1950.47    4817 1952.82  4826.3 1952.36
  4844.2  1958.6  4868.2  1959.6  4984.7 1957.38  4988.8 1954.42  5003.6 1951.42
  5007.4 1952.08  5032.4 1957.28  5048.8 1963.71  5055.7 1968.69  5061.1 1968.51
    5079 1987.66  5084.4 1988.08  5092.5 1993.76  5102.3 2012.03  5107.7 2013.98
  5114.4 2022.64    5131 2027.83  5261.8 2046.94  5432.4 2071.92  5580.5 2079.17
#Mann= 5 ,-1 , 0
  4381.4     .07       0  4809.2     .05       0  4814.3     .07       0
  5007.4      .1       0  5261.8     .07       0
#XS Ineff= 2 , 0
                         4898.12         1958.89
Permanent Ineff=
       F       F
Bank Sta=4809.2,4814.3
XS Rating Curve= 0 ,0
Exp/Cntr=0.3,0.1

Type RM Length L Ch R = 1 ,28435   ,344,344,344
BEGIN DESCRIPTION:
Tegner Creek 56.0
END DESCRIPTION:
XS GIS Cut Line= 4
      1864015.69     13919753.99      1864372.33     13919852.89
      1864535.38     13919839.84      1864847.65     13919589.17
#Sta/Elev= 30
  4627.5 1984.53  4719.9 1979.14  4740.9 1979.74  4759.4 1976.62  4772.1 1976.13
  4792.8 1969.28  4798.8 1965.13    4824 1955.23  4865.5 1946.76  4872.6 1949.62
  4917.3 1950.03  4951.5 1947.92  4985.8 1949.13  5001.4 1948.07  5007.8 1945.82
  5008.1 1945.32  5012.9 1945.82  5020.3 1947.63  5029.6 1946.99  5050.4 1948.77
  5080.5 1954.15  5150.8 1960.67  5207.2  1968.3  5242.4 1971.52  5263.3 1976.36
  5349.6 1992.06    5484 2009.24  5527.2 2013.35    5556 2017.75  5561.6 2019.75
#Mann= 3 ,-1 , 0
  4627.5     .07       0  5007.8     .05       0  5012.9     .07       0
Bank Sta=5007.8,5012.9
XS Rating Curve= 0 ,0
Exp/Cntr=0.3,0.1

Type RM Length L Ch R = 1 ,28091   ,483,483,483
BEGIN DESCRIPTION:
Tegner Creek 55.0
END DESCRIPTION:
XS GIS Cut Line= 3
      1864224.99     13920575.03        1864425.       13920175.
      1864824.96     13919825.03
#Sta/Elev= 30
  4547.8 1996.55  4570.2 1994.79  4592.5 1990.28  4623.3 1987.34  4659.6 1980.69
    4682 1978.39  4718.3 1970.51  4838.5 1958.59  4852.5 1954.53  4869.3 1945.48
  4879.1 1944.56    4928 1944.41  4974.2 1941.93  4998.6 1942.38  4999.5 1940.87
  4999.9 1940.37  5004.9 1940.87    5023 1943.48  5108.5 1943.58  5159.8 1948.58
  5161.9 1948.66  5200.5 1953.84  5257.5 1956.39  5327.7 1963.63  5356.2 1969.06
  5398.9  1973.4  5406.5 1975.94  5453.8 1983.13  5498.6 1991.99  5526.5 1994.29
#Mann= 9 ,-1 , 0
  4547.8     .07       0  4879.1      .1       0  4974.2     .07       0
  4998.6      .1       0  4999.5     .05       0  5004.9      .1       0
  5159.8     .07       0  5161.9      .1       0  5453.8     .07       0
Bank Sta=4999.5,5004.9
XS Rating Curve= 0 ,0
Exp/Cntr=0.3,0.1

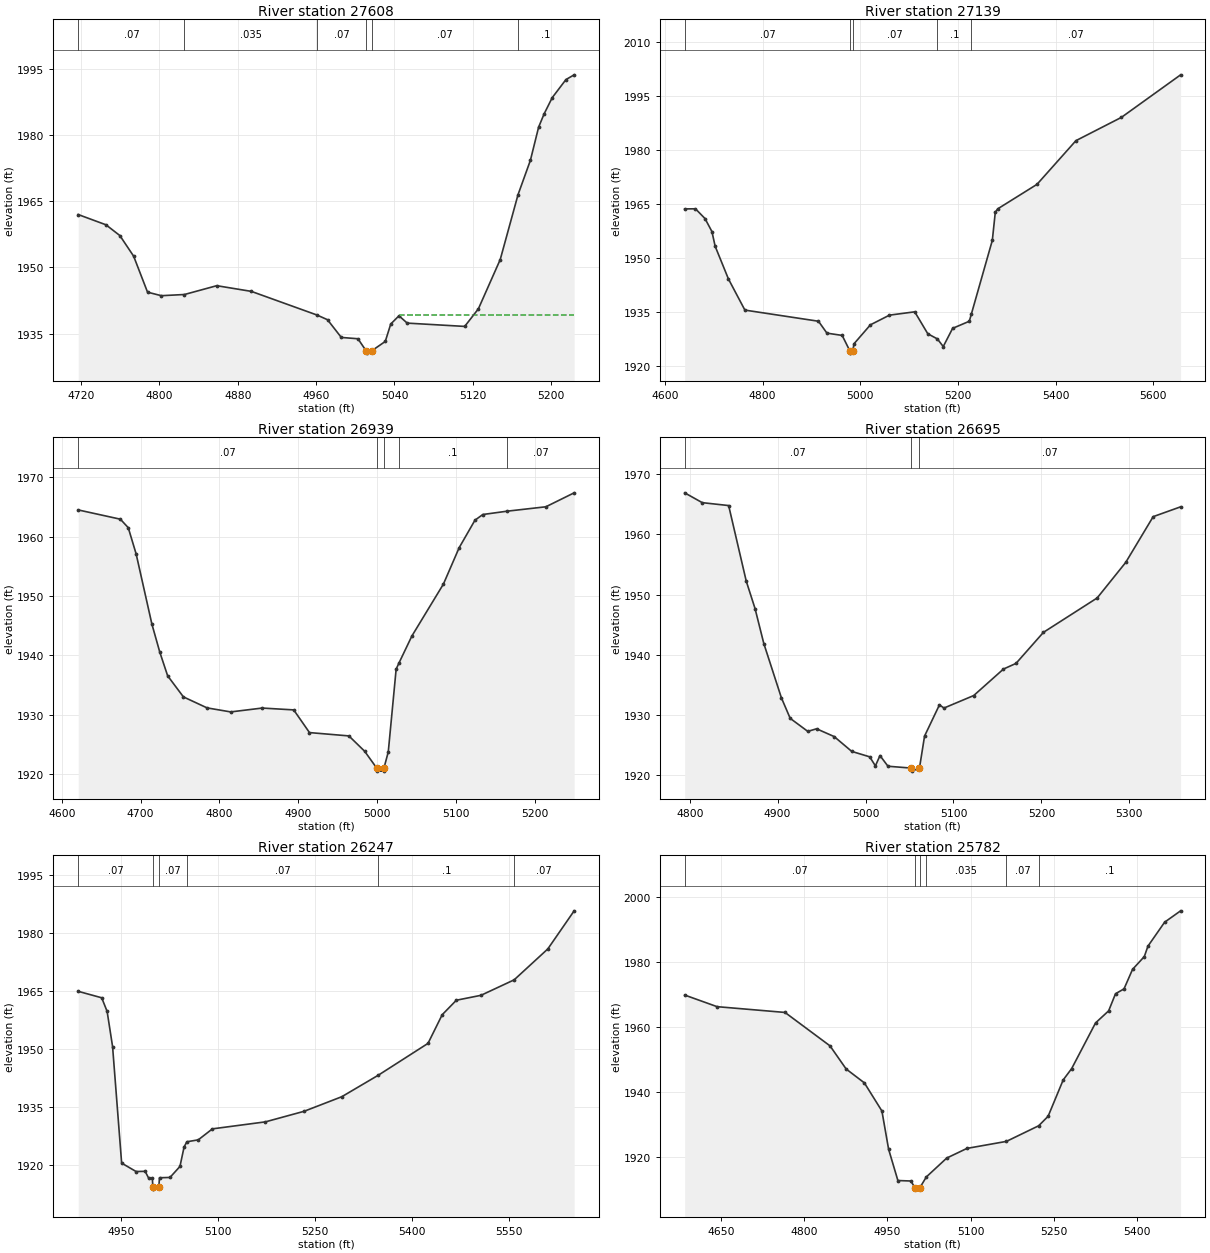
Type RM Length L Ch R = 1 ,27608   ,469,469,469
BEGIN DESCRIPTION:
Tegner Creek 54.0
END DESCRIPTION:
XS GIS Cut Line= 3
      1864674.97     13920475.03        1864875.       13920275.
        1864975.       13920075.
#Sta/Elev= 30
    4717 1961.99  4745.3 1959.67  4759.5 1957.23  4773.6 1952.55  4787.8 1944.38
  4801.9 1943.58  4825.5 1943.85  4858.5 1945.85  4893.8 1944.56  4960.8  1939.2
  4971.6 1938.13  4985.7 1934.11  5002.7 1933.81  5011.1 1931.05  5011.6 1930.55
  5016.6 1931.05  5030.6  1933.2  5036.2 1937.16  5044.6 1939.02    5053 1937.36
  5111.7 1936.61  5125.7  1940.6    5148 1951.78  5166.2 1966.51  5178.8 1974.28
  5187.2 1981.81  5192.8 1984.82  5201.1 1988.51  5215.1 1992.61  5223.5 1993.69
#Mann= 6 ,-1 , 0
    4717     .07       0  4825.5    .035       0  4960.8     .07       0
  5011.1     .05       0  5016.6     .07       0  5166.2      .1       0
#XS Ineff= 2 , 0
                         5045.25         1939.22
Permanent Ineff=
       F       F
Bank Sta=5011.1,5016.6
XS Rating Curve= 0 ,0
Exp/Cntr=0.3,0.1

Type RM Length L Ch R = 1 ,27139   ,200,200,200
BEGIN DESCRIPTION:
Tegner Creek 53.0
END DESCRIPTION:
XS GIS Cut Line= 3
      1864825.01       13920675.       1865246.1     13920554.33
      1865814.32     13920657.79
#Sta/Elev= 30
  4640.6  1963.6  4662.7 1963.63  4682.2 1960.93  4696.4 1957.32    4703 1953.25
  4730.2 1944.18  4763.9 1935.55  4914.6 1932.46  4931.9 1929.16  4963.1 1928.53
  4979.3 1924.12  4979.8 1923.62  4984.8 1924.12  4987.3 1926.21    5021 1931.47
    5060 1934.15  5111.7 1935.07  5138.5 1928.98  5158.1 1927.56  5170.1 1925.44
  5189.3 1930.49  5223.4 1932.45  5227.5 1934.36  5270.6 1954.88  5276.7 1962.69
  5281.8 1963.63  5362.1 1970.41  5441.8 1982.52  5534.9 1988.97  5656.2 2000.77
#Mann= 5 ,-1 , 0
  4640.6     .07       0  4979.3     .05       0  4984.8     .07       0
  5158.1      .1       0  5227.5     .07       0
#XS Ineff= 2 , 0
                         5109.49         1934.77
Permanent Ineff=
       F       F
Bank Sta=4979.3,4984.8
XS Rating Curve= 0 ,0
Exp/Cntr=0.3,0.1

Type RM Length L Ch R = 1 ,26939   ,244,244,244
BEGIN DESCRIPTION:
Tegner Creek 52.1
END DESCRIPTION:
XS GIS Cut Line= 2
      1864821.51     13920750.59      1865450.91     13920748.42
#Sta/Elev= 30
  4620.8 1964.48  4674.3 1962.92  4684.3 1961.49  4694.3 1957.08  4714.3 1945.26
  4724.3 1940.55  4734.3 1936.55  4754.3    1933  4784.3 1931.15  4814.3 1930.47
  4854.3 1931.12  4894.3 1930.81  4914.3 1926.99  4964.3 1926.43  4984.3 1923.85
  4999.7    1921  5000.2  1920.5  5008.3  1920.5  5008.8    1921  5014.3 1923.74
  5024.3 1937.68  5027.9 1938.71  5044.3 1943.26  5084.3    1952  5104.3 1958.13
  5124.3 1962.75  5134.3 1963.71  5165.2 1964.27  5214.3 1965.01  5250.2 1967.36
#Mann= 5 ,-1 , 0
  4620.8     .07       0  4999.7     .05       0  5008.8     .07       0
  5027.9      .1       0  5165.2     .07       0
Bank Sta=4999.7,5008.8
XS Rating Curve= 0 ,0
Exp/Cntr=0.3,0.1

Type RM Length L Ch R = 1 ,26695   ,448,448,448
BEGIN DESCRIPTION:
Tegner Creek 52.0
END DESCRIPTION:
XS GIS Cut Line= 3
        1864825.       13920925.        1865025.       13920925.
      1865374.99       13920825.
#Sta/Elev= 30
  4794.3 1966.86  4814.3 1965.23  4844.3 1964.75  4864.3 1952.23  4874.3 1947.68
  4884.3 1941.87  4904.3 1932.87  4914.3 1929.47  4934.3 1927.31  4944.3 1927.74
  4964.3 1926.45  4984.3 1923.99  5004.7 1923.09  5011.2 1921.59  5016.4  1923.3
  5025.5 1921.53  5052.2 1921.22  5052.7 1920.72  5061.3 1921.22  5067.1 1926.53
    5084  1931.7  5089.2 1931.18    5123 1933.25  5156.8 1937.64  5171.1 1938.58
  5202.3 1943.73  5263.4 1949.43  5295.9 1955.33  5327.1 1962.91  5358.3 1964.54
#Mann= 3 ,-1 , 0
  4794.3     .07       0  5052.2     .05       0  5061.3     .07       0
Bank Sta=5052.2,5061.3
XS Rating Curve= 0 ,0
Exp/Cntr=0.3,0.1

Type RM Length L Ch R = 1 ,26247   ,465,465,465
BEGIN DESCRIPTION:
Tegner Creek 51.0
END DESCRIPTION:
XS GIS Cut Line= 3
      1864975.03     13921374.99        1865075.       13921325.
      1865650.82     13921013.81
#Sta/Elev= 30
  4883.9 1964.95  4920.2 1963.28  4928.6 1959.74    4937 1950.67    4951 1920.55
  4973.3 1918.37  4987.3 1918.42  4992.9 1916.61  4998.5 1916.61  4999.2 1914.32
  4999.7 1913.82  5008.4 1914.32  5009.5 1916.76  5025.7 1916.84  5041.1 1919.68
  5047.5 1924.72  5051.8 1926.06  5069.4 1926.56  5091.3  1929.4  5173.2 1931.21
  5233.1 1933.95  5291.2 1937.71  5347.8 1943.29  5424.4  1951.5  5446.3  1958.9
  5468.2 1962.65  5506.2 1963.92  5557.5 1967.92  5609.5 1975.91  5650.2 1985.76
#Mann= 6 ,-1 , 0
  4883.9     .07       0  4999.2     .05       0  5008.4     .07       0
  5051.8     .07       0  5347.8      .1       0  5557.5     .07       0
Bank Sta=4999.2,5008.4
XS Rating Curve= 0 ,0
Exp/Cntr=0.3,0.1

Type RM Length L Ch R = 1 ,25782   ,447,447,447
BEGIN DESCRIPTION:
Tegner Creek 50.0
END DESCRIPTION:
XS GIS Cut Line= 3
      1865038.37     13921794.24        1865425.       13921625.
      1865824.96     13921375.02
#Sta/Elev= 30
  4584.7 1969.78  4643.1  1966.2  4765.5 1964.42  4846.6 1954.12  4875.7 1946.99
  4908.5 1942.72  4940.1 1934.06  4952.2 1922.26  4968.9 1912.63  4992.3 1912.48
  4999.4 1910.48  4999.9 1909.98  5008.7 1910.48  5020.2 1913.74  5056.9 1919.55
  5093.4 1922.53  5164.5 1924.69  5222.6  1929.5  5239.6 1932.42  5266.8 1943.63
  5282.1 1947.13  5325.1 1961.19  5348.7 1964.91  5361.1 1970.19  5376.4 1971.68
  5391.8  1977.7    5413 1981.64  5419.5 1984.84  5449.6 1992.23  5478.4 1995.73
#Mann= 6 ,-1 , 0
  4584.7     .07       0  4999.4     .05       0  5008.7     .07       0
  5020.2    .035       0  5164.5     .07       0  5222.6      .1       0
Bank Sta=4999.4,5008.7
XS Rating Curve= 0 ,0
Exp/Cntr=0.3,0.1

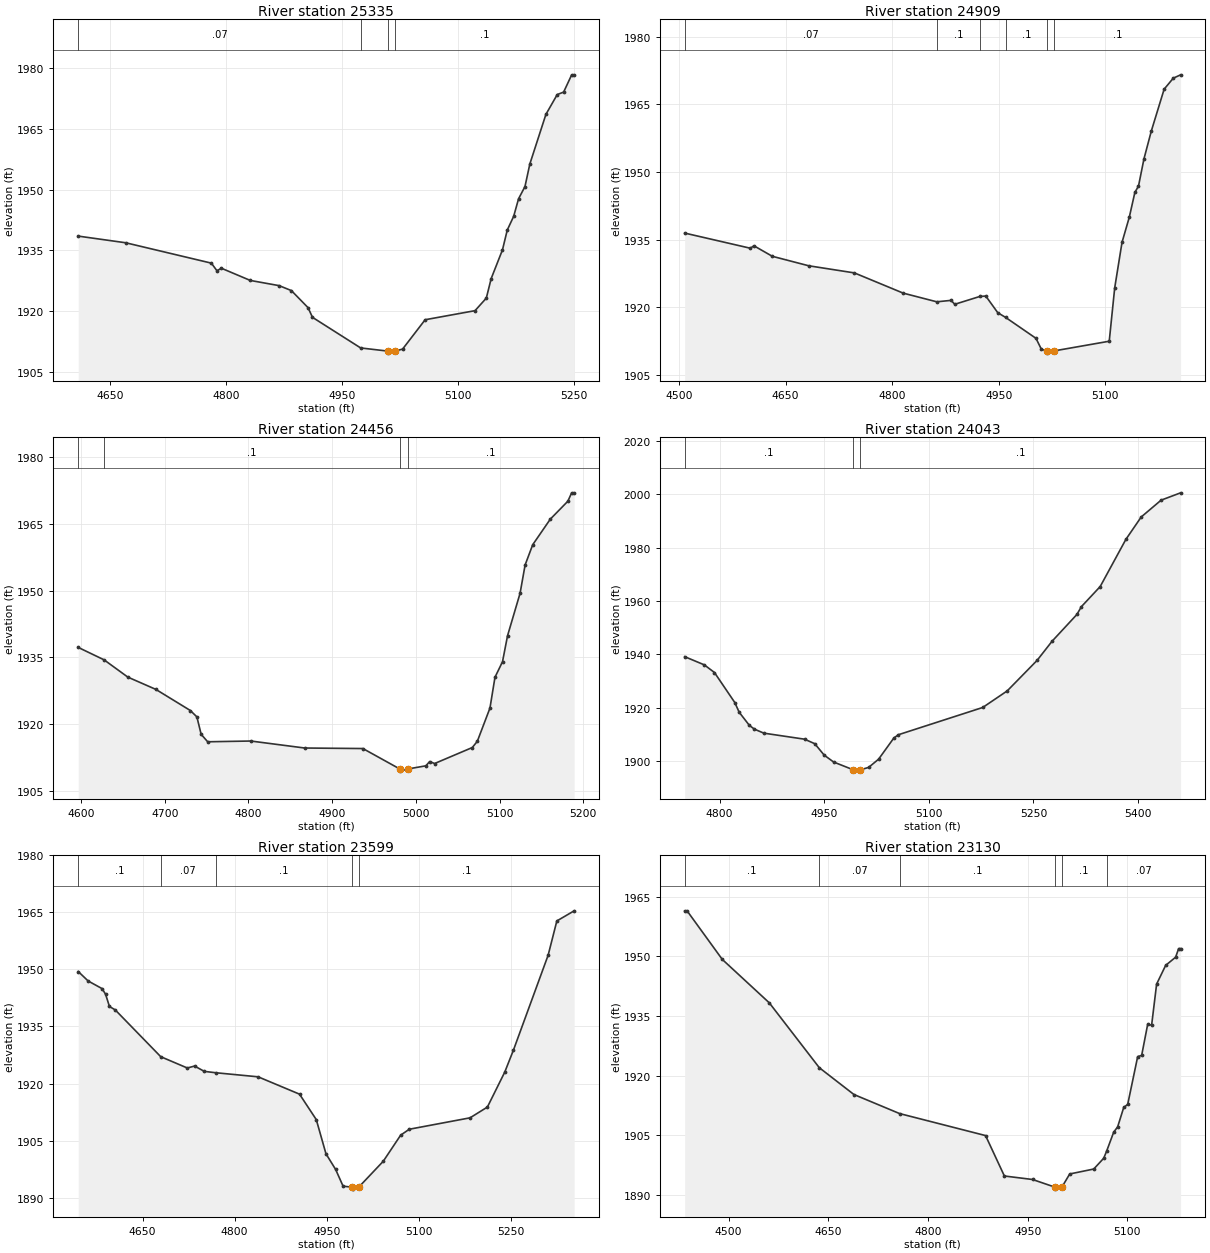
Type RM Length L Ch R = 1 ,25335   ,426,426,426
BEGIN DESCRIPTION:
Tegner Creek 49.0
END DESCRIPTION:
XS GIS Cut Line= 3
      1865435.79      13922070.2        1865775.       13921875.
      1865925.02     13921674.97
#Sta/Elev= 30
  4608.4 1938.49  4669.9 1936.84  4780.6 1931.81  4787.8 1929.94  4793.6 1930.55
  4830.9 1927.54  4868.3 1926.25  4884.1 1925.03  4905.6 1920.82  4911.4 1918.42
  4973.7 1910.86  5008.7 1910.08  5009.2 1909.58    5018 1910.08  5027.9 1910.57
  5057.1 1917.83  5121.6 1920.07  5136.2 1923.17  5142.5    1928  5157.1 1935.09
  5163.3 1939.99  5171.6 1943.38  5177.9 1947.71  5186.2 1950.73  5192.5 1956.31
  5213.3 1968.57  5227.9 1973.45  5236.2 1974.07  5246.6 1978.33  5249.8 1978.33
#Mann= 4 ,-1 , 0
  4608.4     .07       0  4973.7      .1       0  5008.7     .05       0
    5018      .1       0
Bank Sta=5008.7,5018
XS Rating Curve= 0 ,0
Exp/Cntr=0.3,0.1

Type RM Length L Ch R = 1 ,24909   ,453,453,453
BEGIN DESCRIPTION:
Tegner Creek 48.0
END DESCRIPTION:
XS GIS Cut Line= 3
      1865494.53     13922119.05        1865975.       13922225.
      1866175.03     13922275.01
#Sta/Elev= 30
  4507.9 1936.43  4600.3 1933.07  4605.4 1933.61  4631.3 1931.28  4682.5 1929.18
  4746.8  1927.6  4815.6 1923.11  4862.8 1921.19    4883 1921.51  4888.1 1920.64
  4923.3 1922.37  4931.8 1922.47  4948.7 1918.77  4959.6 1917.74  5002.5 1913.09
  5010.2 1910.63  5018.1 1910.31  5018.6 1909.81  5028.2 1910.31  5105.6 1912.45
  5113.3 1924.27  5123.6 1934.37  5133.9 1939.98  5141.7 1945.45  5146.8 1946.85
  5154.5 1952.89  5164.8 1959.03  5182.9 1968.34  5195.8 1970.78  5206.1 1971.52
#Mann= 6 ,-1 , 0
  4507.9     .07       0  4862.8      .1       0  4923.3    .035       0
  4959.6      .1       0  5018.1     .05       0  5028.2      .1       0
Bank Sta=5018.1,5028.2
XS Rating Curve= 0 ,0
Exp/Cntr=0.3,0.1

Type RM Length L Ch R = 1 ,24456   ,413,413,413
BEGIN DESCRIPTION:
Tegner Creek 47.0
END DESCRIPTION:
XS GIS Cut Line= 3
      1865424.96     13922424.99        1865825.       13922525.
      1865974.98     13922624.98
#Sta/Elev= 30
  4596.6 1937.26  4627.5 1934.47  4655.9 1930.59  4689.4 1927.83  4730.6 1923.09
  4738.4 1921.66  4743.5 1917.75  4751.3 1916.07  4802.8 1916.24  4867.2 1914.67
  4936.8 1914.55  4980.7 1909.98  4981.2 1909.48  4990.9 1909.98    5012 1910.67
  5016.5 1911.62  5022.5 1911.19  5067.5 1914.78  5073.5 1916.18  5088.6 1923.64
  5094.6 1930.56  5103.6 1934.05  5109.6 1939.88  5124.6 1949.43  5130.6 1955.77
  5139.7 1960.32  5160.7 1966.06  5181.7 1970.09  5186.2 1971.97  5189.2 1971.97
#Mann= 4 ,-1 , 0
  4596.6     .07       0  4627.5      .1       0  4980.7     .05       0
  4990.9      .1       0
Bank Sta=4980.7,4990.9
XS Rating Curve= 0 ,0
Exp/Cntr=0.3,0.1

Type RM Length L Ch R = 1 ,24043   ,444,444,444
BEGIN DESCRIPTION:
Tegner Creek 46.0
END DESCRIPTION:
XS GIS Cut Line= 3
        1865325.       13922625.        1865525.       13922775.
      1865875.02     13923075.02
#Sta/Elev= 30
    4750 1939.17  4778.1 1936.11  4792.7 1933.24  4821.9 1921.99  4828.1 1918.39
  4842.7 1913.47    4850 1912.04  4863.5 1910.55  4921.9 1908.29  4936.5  1906.6
    4950 1902.33  4963.5 1899.75  4991.7 1896.84  4992.2 1896.34    5002 1896.84
  5013.7 1897.73    5028 1900.81  5049.9 1908.74  5056.5 1909.97  5177.3 1920.16
  5212.4 1926.36  5255.2 1937.77  5276.6 1944.91  5312.3 1954.96  5318.8  1957.9
  5345.7 1965.41  5382.5 1983.05  5404.5 1991.44    5433 1997.73    5461 2000.48
#Mann= 3 ,-1 , 0
    4750      .1       0  4991.7     .05       0    5002      .1       0
Bank Sta=4991.7,5002
XS Rating Curve= 0 ,0
Exp/Cntr=0.3,0.1

Type RM Length L Ch R = 1 ,23599   ,469,469,469
BEGIN DESCRIPTION:
Tegner Creek 45.0
END DESCRIPTION:
XS GIS Cut Line= 3
      1864830.93     13922847.97        1865225.       13923075.
      1865474.97     13923324.97
#Sta/Elev= 30
    4545 1949.45  4561.2 1946.96  4583.8 1944.96  4589.6 1943.48  4595.9 1940.26
  4605.4 1939.35  4679.5 1927.06  4722.8 1924.09  4734.7  1924.6  4750.5  1923.2
  4769.2 1922.84  4838.2 1921.77  4905.7 1917.21    4933 1910.53  4948.8 1901.54
  4964.6 1897.41  4976.7 1893.03  4991.8 1892.75  4992.3 1892.25  5002.1 1892.75
  5042.2 1899.58  5070.5 1906.43  5084.6 1907.99  5183.6 1910.99  5211.9 1913.82
  5240.2 1923.01  5254.4 1928.81  5310.9 1953.73  5325.1 1962.74  5353.3  1965.4
#Mann= 5 ,-1 , 0
    4545      .1       0  4679.5     .07       0  4769.2      .1       0
  4991.8     .05       0  5002.1      .1       0
Bank Sta=4991.8,5002.1
XS Rating Curve= 0 ,0
Exp/Cntr=0.3,0.1

Type RM Length L Ch R = 1 ,23130   ,485,485,485
BEGIN DESCRIPTION:
Tegner Creek 44.0
END DESCRIPTION:
XS GIS Cut Line= 3
      1864524.98     13923024.98        1864925.       13923425.
        1865025.     13923575.01
#Sta/Elev= 30
    4434  1961.4  4437.6  1961.4  4490.6 1949.18  4561.3 1938.27  4636.5 1921.97
  4688.6 1915.23  4757.3 1910.44  4886.6 1904.91  4914.9 1894.75  4957.3 1893.87
  4990.9 1891.95  4991.4 1891.45  5001.4 1891.95  5013.2 1895.26  5049.3  1896.5
  5064.3 1899.21  5068.6 1900.95  5079.3 1905.75  5085.3 1907.11  5094.4 1911.97
  5100.4 1912.75  5115.4 1924.75  5121.4 1925.06  5130.4 1932.83  5136.4 1932.68
  5143.9 1942.99  5157.5 1947.69  5172.5 1949.75    5177  1951.9    5180  1951.9
#Mann= 6 ,-1 , 0
    4434      .1       0  4636.5     .07       0  4757.3      .1       0
  4990.9     .05       0  5001.4      .1       0  5068.6     .07       0
Bank Sta=4990.9,5001.4
XS Rating Curve= 0 ,0
Exp/Cntr=0.3,0.1

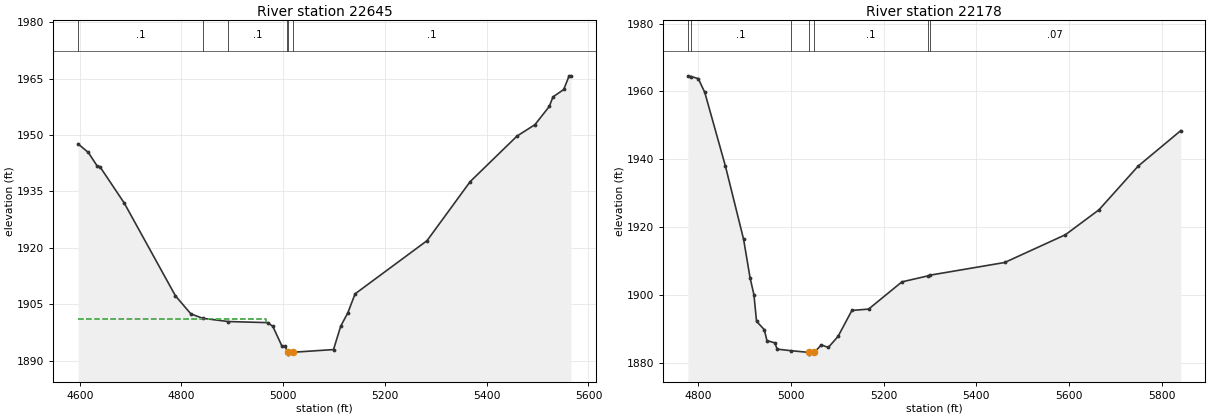
Type RM Length L Ch R = 1 ,22645   ,467,467,467
BEGIN DESCRIPTION:
Tegner Creek 43.0
END DESCRIPTION:
XS GIS Cut Line= 3
      1864425.01     13923125.05        1864475.       13923525.
      1864874.97     13923924.97
#Sta/Elev= 30
  4596.8 1947.65  4616.9 1945.37  4634.5 1941.74  4639.6 1941.62  4687.5 1931.94
  4788.2 1907.27  4818.5 1902.47  4841.8 1901.29  4892.2 1900.43  4969.6 1900.14
  4979.7 1899.13  4997.3 1893.97  5003.4 1893.97    5008 1892.49  5008.7 1892.27
  5009.2 1891.77  5019.3 1892.27  5098.9 1892.98    5113 1899.18  5127.1 1902.77
  5141.3 1907.79  5282.7 1921.92  5367.6 1937.63  5459.5 1949.71  5494.8 1952.75
  5523.1 1957.61  5530.2 1960.12  5551.4  1962.1    5562 1965.73  5565.5 1965.73
#Mann= 6 ,-1 , 0
  4596.8      .1       0  4841.8     .07       0  4892.2      .1       0
    5008      .1       0  5008.7     .05       0  5019.3      .1       0
#XS Ineff= 2 , 0
         4967.03 1901.02
Permanent Ineff=
       F       F
Bank Sta=5008.7,5019.3
XS Rating Curve= 0 ,0
Exp/Cntr=0.3,0.1

Type RM Length L Ch R = 1 ,22178   ,451,451,451
BEGIN DESCRIPTION:
Tegner Creek 42.0
END DESCRIPTION:
XS GIS Cut Line= 3
      1863825.01     13923375.01        1864025.       13923475.
      1864721.14     13923945.29
#Sta/Elev= 30
  4777.4 1964.58  4784.3 1964.38  4799.7 1963.76  4813.7 1959.72  4858.4 1937.92
  4897.6 1916.33  4911.5 1905.02  4919.9 1899.98  4925.5 1892.17  4942.3 1889.69
  4947.9 1886.48  4964.7 1885.83  4970.2 1883.96  4998.9 1883.52  5038.9 1882.99
  5039.4 1882.49  5049.9 1882.99  5065.4 1885.22  5080.4 1884.46  5101.4 1887.71
  5131.3 1895.38  5167.3 1895.77  5239.2  1903.8  5295.7 1905.58    5299 1905.76
  5461.1 1909.52  5592.3 1917.72  5664.7 1925.08  5749.2 1937.96  5841.1 1948.42
#Mann= 7 ,-1 , 0
  4777.4     .07       0  4784.3      .1       0  4998.9      .1       0
  5038.9     .05       0  5049.9      .1       0  5295.7      .1       0
    5299     .07       0
Bank Sta=5038.9,5049.9
XS Rating Curve= 0 ,0
Exp/Cntr=0.3,0.1