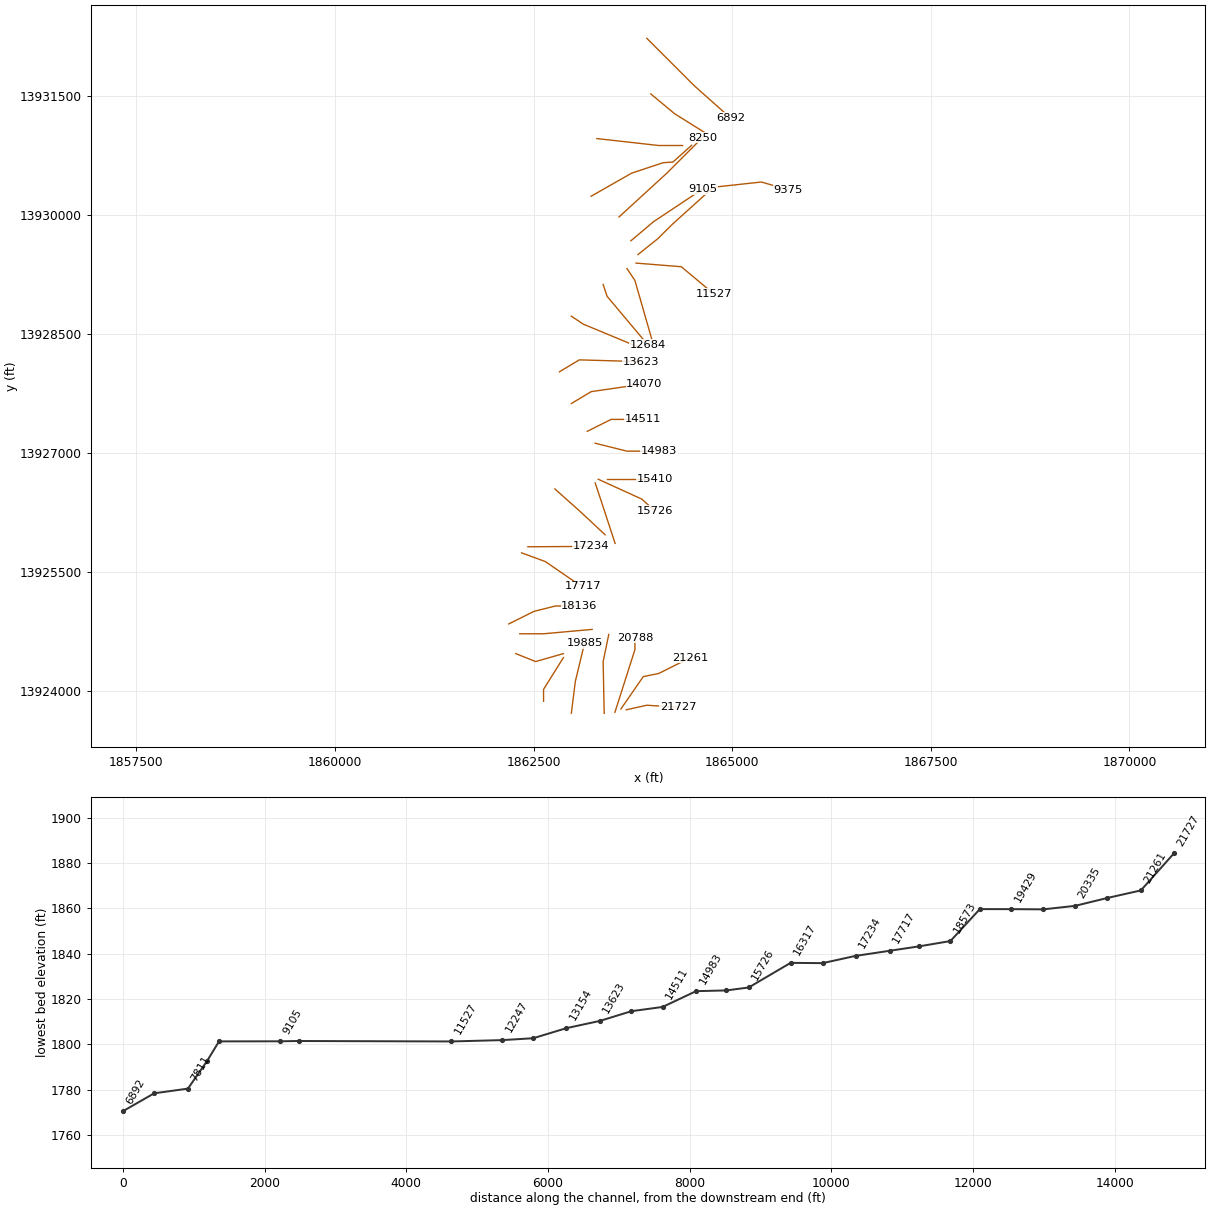
HEC-RAS study Tegener Creek.prj: Tegener Creek Base Level Engineering

--- Tegener Creek.g01 (geometry) --- (continued)

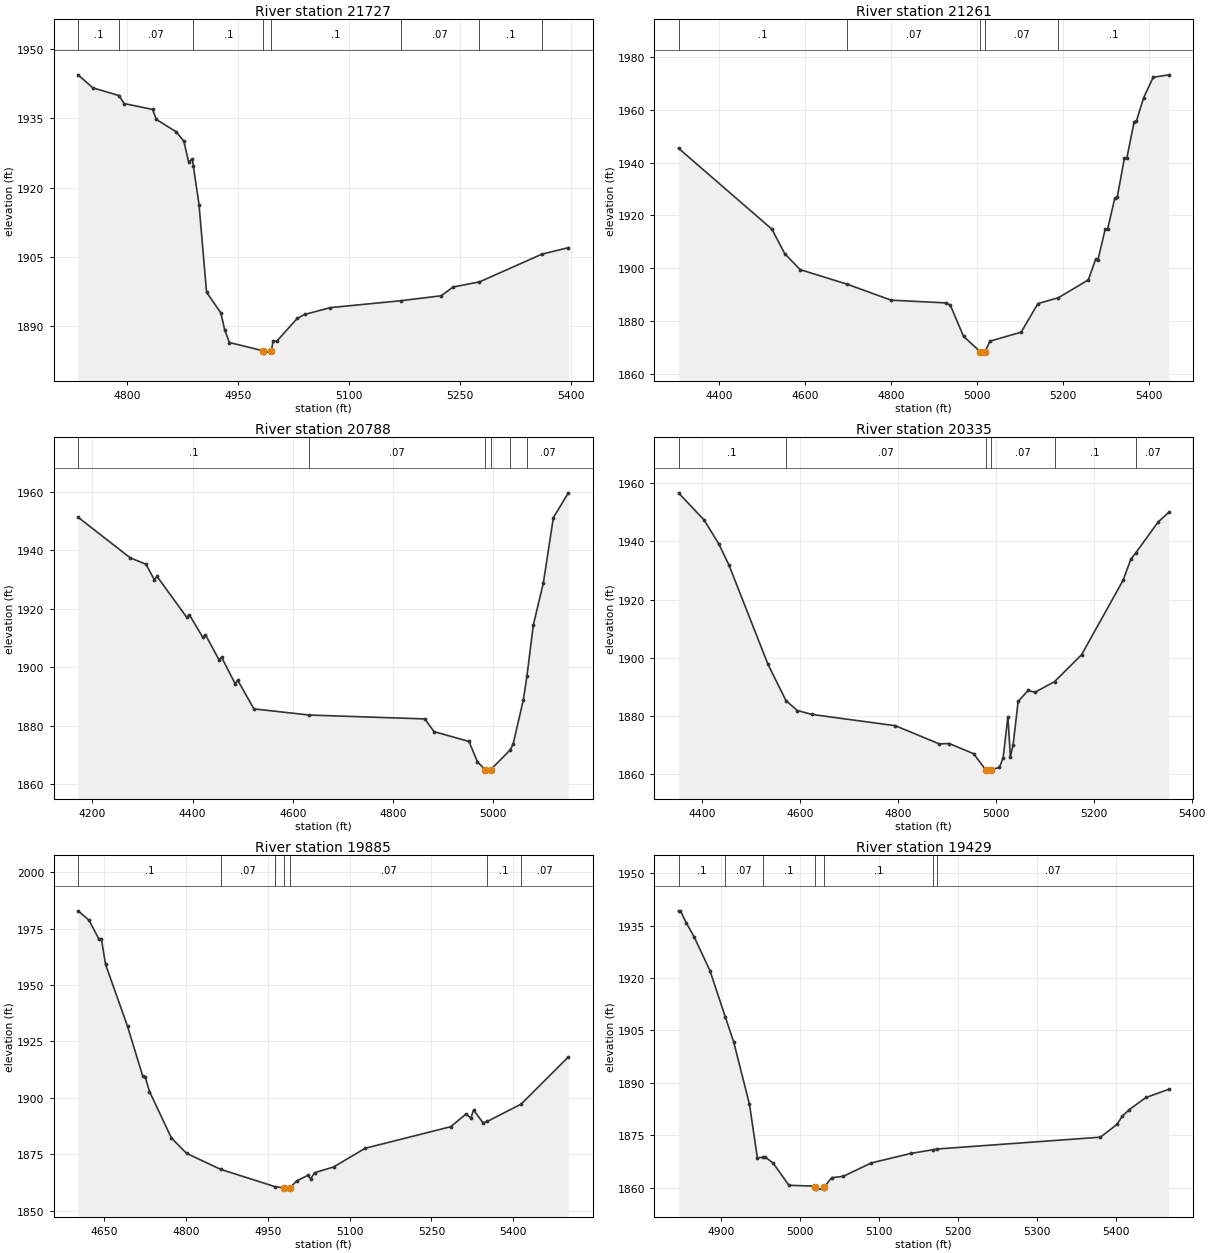
Type RM Length L Ch R = 1 ,21727   ,466,466,466
BEGIN DESCRIPTION:
Tegner Creek 41.0
END DESCRIPTION:
XS GIS Cut Line= 3
       1863665.6     13923767.34        1863925.       13923825.
      1864320.38     13923798.43
#Sta/Elev= 30
  4734.3 1944.43  4754.2 1941.62  4789.7 1939.93  4796.5 1938.21  4834.9 1936.94
    4840 1934.78  4866.9 1932.08  4877.1 1930.07  4883.5 1925.61  4888.6 1926.19
    4890 1924.66  4897.6 1916.34  4907.8 1897.36  4927.1 1892.89  4932.2 1889.26
  4938.6 1886.49  4984.3 1884.69  4984.8 1884.19  4995.3 1884.69  4997.5 1886.76
  5002.5 1886.76  5030.1 1891.69  5040.1 1892.56  5074.9 1894.04  5170.4 1895.54
  5224.7 1896.61  5240.6  1898.5  5276.2 1899.61  5360.7 1905.62  5396.3 1907.02
#Mann= 8 ,-1 , 0
  4734.3      .1       0  4789.7     .07       0    4890      .1       0
  4984.3     .05       0  4995.3      .1       0  5170.4     .07       0
  5276.2      .1       0  5360.7     .07       0
Bank Sta=4984.3,4995.3
XS Rating Curve= 0 ,0
Exp/Cntr=0.3,0.1

Type RM Length L Ch R = 1 ,21261   ,473,473,473
BEGIN DESCRIPTION:
Tegner Creek 40.0
END DESCRIPTION:
XS GIS Cut Line= 4
       1863598.6       13923778.      1863880.01     13924185.14
        1864075.       13924225.      1864475.04     13924425.02
#Sta/Elev= 30
  4305.6 1945.44    4523  1914.8  4552.7 1905.56  4588.5  1899.5  4698.9 1893.92
  4800.5 1887.92  4928.9 1886.88  4938.3 1885.98  4968.9 1874.25    5008 1868.37
  5008.5 1867.87    5019 1868.37  5030.3  1872.4    5103  1875.8  5142.1 1886.62
  5189.9 1888.85  5259.5 1895.62  5276.3 1903.37  5281.9 1903.31  5298.6 1914.72
  5304.2 1914.78    5321 1926.54  5326.6 1926.81  5343.3 1941.64  5348.9 1941.62
  5365.7 1955.19  5371.3 1955.71  5388.1 1964.57  5410.4 1972.31  5446.8 1973.23
#Mann= 5 ,-1 , 0
  4305.6      .1       0  4698.9     .07       0    5008     .05       0
    5019     .07       0  5189.9      .1       0
Bank Sta=5008,5019
XS Rating Curve= 0 ,0
Exp/Cntr=0.3,0.1

Type RM Length L Ch R = 1 ,20788   ,453,453,453
BEGIN DESCRIPTION:
Tegner Creek 39.0
END DESCRIPTION:
XS GIS Cut Line= 3
      1863523.37     13923735.96        1863775.       13924525.
        1863775.     13924675.01
#Sta/Elev= 30
  4171.7 1951.28  4275.7 1937.41  4307.1 1935.22    4324  1929.9  4329.3 1931.06
  4388.4  1917.1  4393.7 1917.99  4420.6 1910.21  4425.9 1911.14  4452.8 1902.59
  4458.1  1903.4    4485 1894.42  4490.3 1895.57  4522.5  1885.8  4632.9  1883.7
  4863.4 1882.38  4881.9 1878.03  4951.6 1874.68  4968.4 1867.73  4983.8 1865.04
  4984.3 1864.54  4994.9 1865.04  5033.9 1871.82  5039.9 1873.97  5059.9 1888.82
  5067.2 1897.03  5079.9 1914.45  5099.9 1928.82  5119.9 1951.15  5149.9 1959.61
#Mann= 6 ,-1 , 0
  4171.7      .1       0  4632.9     .07       0  4983.8     .05       0
  4994.9     .07       0  5033.9      .1       0  5067.2     .07       0
Bank Sta=4983.8,4994.9
XS Rating Curve= 0 ,0
Exp/Cntr=0.3,0.1

Type RM Length L Ch R = 1 ,20335   ,450,450,450
BEGIN DESCRIPTION:
Tegner Creek 38.0
END DESCRIPTION:
XS GIS Cut Line= 3
      1863388.21     13923722.32        1863375.       13924375.
      1863445.74     13924716.43
#Sta/Elev= 30
  4351.9 1956.72  4404.6  1947.3  4434.6 1939.04  4454.6 1932.05  4534.6 1897.81
  4571.4 1885.32  4594.6  1881.9  4624.6 1880.56  4794.7 1876.69  4884.7 1870.43
  4904.7 1870.57  4954.7 1867.07  4979.2 1861.58  4979.7 1861.08  4990.3 1861.58
  5007.3 1862.34  5014.9 1865.65  5024.7 1879.84  5029.8 1865.94  5035.4 1870.23
  5045.6 1885.05    5066  1888.8    5080 1888.19    5120 1891.85  5175.2 1901.11
    5260 1926.69  5275.6 1933.85    5286 1936.13  5331.5  1946.7  5353.4 1950.04
#Mann= 6 ,-1 , 0
  4351.9      .1       0  4571.4     .07       0  4979.2     .05       0
  4990.3     .07       0    5120      .1       0    5286     .07       0
Bank Sta=4979.2,4990.3
XS Rating Curve= 0 ,0
Exp/Cntr=0.3,0.1

Type RM Length L Ch R = 1 ,19885   ,456,456,456
BEGIN DESCRIPTION:
Tegner Creek 37.0
END DESCRIPTION:
XS GIS Cut Line= 3
        1862975.     13923725.01        1863025.       13924125.
      1863141.12     13924607.32
#Sta/Elev= 30
  4601.9 1982.86    4622  1978.7  4639.7 1970.53  4644.7 1970.38  4652.3 1959.12
  4692.6 1931.69  4720.3 1909.76  4725.3    1909  4732.9 1902.78  4773.2 1882.15
  4800.9 1875.38  4863.2  1868.3  4962.7 1860.65  4979.3 1860.02  4979.8 1859.52
  4990.4 1860.02  5002.5 1863.11  5023.4 1865.65  5028.5 1864.12  5035.9  1866.8
  5070.5 1869.34  5128.4 1877.62  5285.3 1887.19  5313.6 1892.87  5322.1 1890.96
  5327.2 1894.58  5344.4 1888.95  5352.1  1889.5  5414.4  1897.2  5501.1 1918.13
#Mann= 8 ,-1 , 0
  4601.9      .1       0  4863.2     .07       0  4962.7    .035       0
  4962.7     .07       0  4979.3     .05       0  4990.4     .07       0
  5352.1      .1       0  5414.4     .07       0
Bank Sta=4979.3,4990.4
XS Rating Curve= 0 ,0
Exp/Cntr=0.3,0.1

Type RM Length L Ch R = 1 ,19429   ,441,441,441
BEGIN DESCRIPTION:
Tegner Creek 36.0
END DESCRIPTION:
XS GIS Cut Line= 3
        1862625.       13923875.        1862625.       13924025.
        1862875.       13924425.
#Sta/Elev= 30
  4845.8 1939.21  4848.3 1939.21  4855.8 1935.69  4865.8  1931.7  4885.8 1922.03
  4905.2 1908.83  4915.8 1901.68  4935.8 1883.87  4945.8 1868.54  4953.2 1868.73
  4955.8 1868.79  4965.8 1867.05  4985.8 1860.71  5018.8 1860.46  5019.1 1860.11
  5019.6 1859.61  5029.8 1859.61  5030.3 1860.11    5040 1862.87  5054.8 1863.28
  5090.1 1867.09  5140.3 1869.82  5168.7 1870.89  5173.8 1871.09  5380.8 1874.47
    5402 1878.18  5408.5  1880.5  5417.4 1882.38  5438.6 1885.83  5467.5 1888.17
#Mann= 7 ,-1 , 0
  4845.8      .1       0  4905.2     .07       0  4953.2      .1       0
  5019.1     .05       0  5030.3      .1       0  5168.7    .035       0
  5173.8     .07       0
Bank Sta=5019.1,5030.3
XS Rating Curve= 0 ,0
Exp/Cntr=0.3,0.1

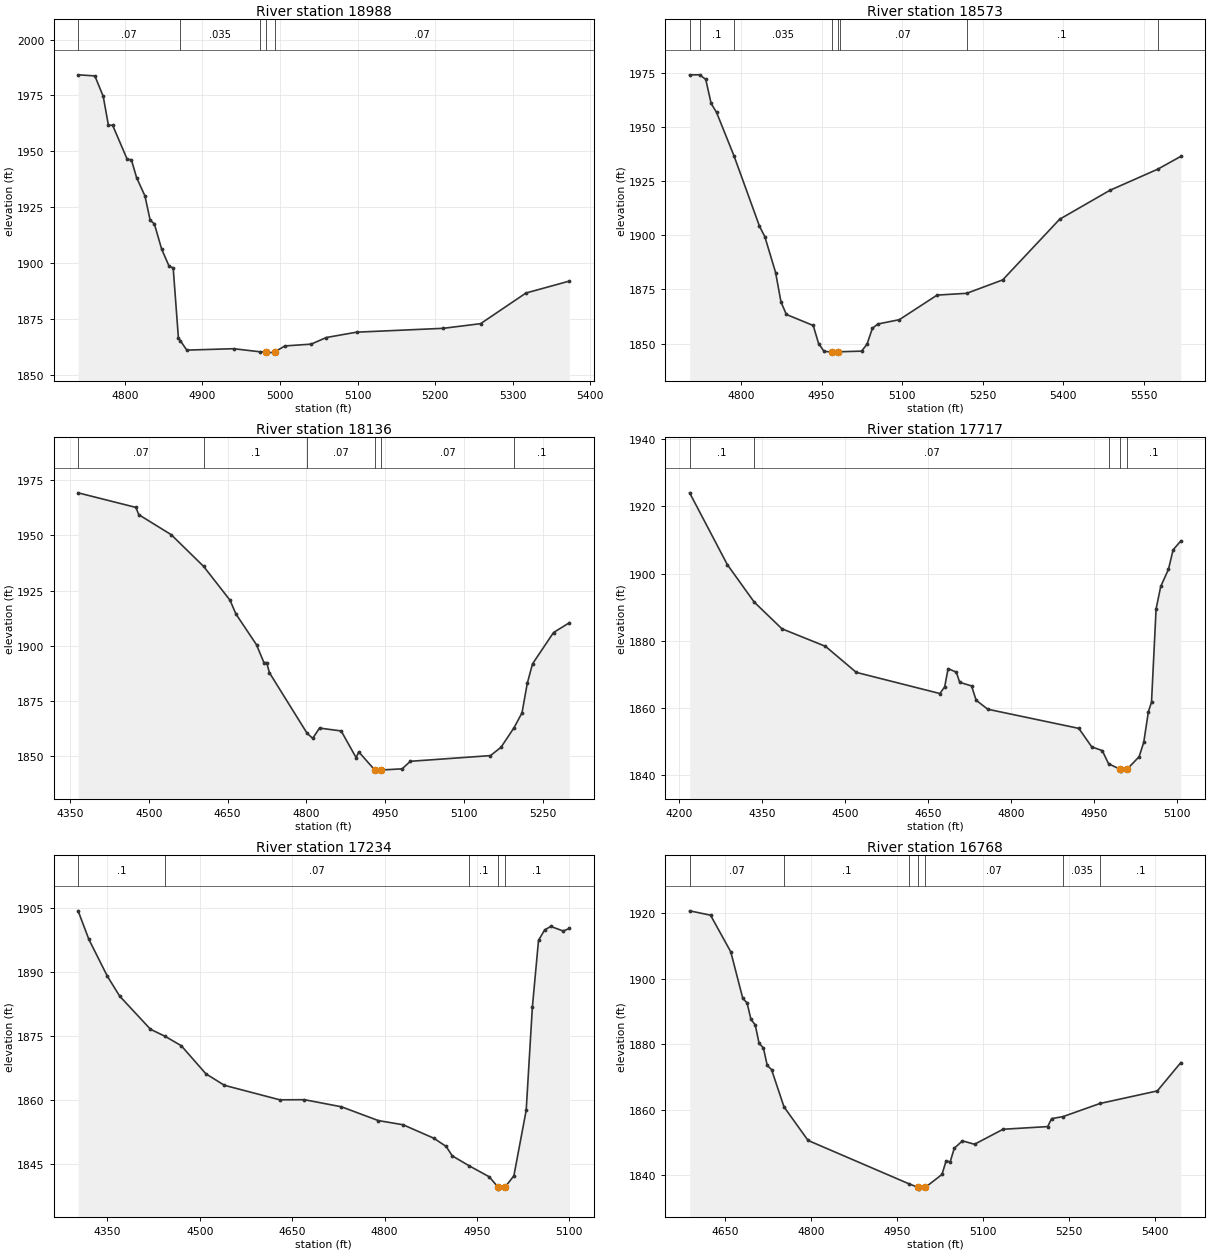
Type RM Length L Ch R = 1 ,18988   ,415,415,415
BEGIN DESCRIPTION:
Tegner Creek 35.0
END DESCRIPTION:
XS GIS Cut Line= 3
      1862274.96     13924475.01        1862525.       13924375.
        1862875.       13924475.
#Sta/Elev= 30
  4739.7 1984.23  4761.3 1983.76  4772.1 1974.58  4778.8 1961.64  4784.2 1961.67
    4803 1946.42  4808.4 1946.19  4815.1 1938.23  4825.9 1929.99  4832.6 1919.14
    4838 1917.51  4847.4 1906.23  4856.9 1898.62  4862.3 1897.76    4869  1866.5
  4871.4 1865.27  4879.8 1860.98  4940.3 1861.61  4973.7 1860.25  4981.8 1860.13
  4982.3 1859.63  4993.1 1860.13  5006.3 1862.85  5040.2 1863.66  5059.7 1866.62
  5098.7 1869.01  5210.5 1870.74  5258.6 1872.82  5317.1 1886.54    5373 1891.88
#Mann= 5 ,-1 , 0
  4739.7     .07       0  4871.4    .035       0  4973.7     .07       0
  4981.8     .05       0  4993.1     .07       0
Bank Sta=4981.8,4993.1
XS Rating Curve= 0 ,0
Exp/Cntr=0.3,0.1

Type RM Length L Ch R = 1 ,18573   ,437,437,437
BEGIN DESCRIPTION:
Tegner Creek 34.0
END DESCRIPTION:
XS GIS Cut Line= 3
      1862325.05       13924725.        1862625.       13924725.
      1863236.78     13924780.03
#Sta/Elev= 30
  4704.5 1974.22  4723.3 1974.24  4734.5 1972.11  4744.5 1961.02  4754.5 1956.91
    4787 1936.82  4834.5 1904.24  4844.5 1899.36  4864.5 1882.83  4874.5 1869.23
  4884.5 1863.44  4934.5 1858.33  4944.5 1849.99  4954.5 1846.41  4968.8 1846.05
  4969.3 1845.55  4980.1 1846.05  4984.1 1846.19  5024.5 1846.47  5034.6 1849.68
  5044.6 1857.01  5054.7 1859.01  5094.8 1861.02  5165.1 1872.39  5220.2 1873.21
  5287.1 1879.41  5393.1 1907.46  5486.4 1920.81  5575.6  1930.6  5618.7 1936.54
#Mann= 8 ,-1 , 0
  4704.5     .07       0  4723.3      .1       0    4787    .035       0
  4968.8     .05       0  4980.1    .035       0  4984.1     .07       0
  5220.2      .1       0  5575.6     .07       0
Bank Sta=4968.8,4980.1
XS Rating Curve= 0 ,0
Exp/Cntr=0.3,0.1

Type RM Length L Ch R = 1 ,18136   ,419,419,419
BEGIN DESCRIPTION:
Tegner Creek 33.0
END DESCRIPTION:
XS GIS Cut Line= 4
      1862186.24     13924848.68      1862505.06     13925007.51
        1862775.       13925075.      1863074.96       13925075.
#Sta/Elev= 30
  4365.6 1969.25  4475.5 1962.65  4481.1 1959.34  4542.7  1950.3  4604.5 1935.91
  4654.6 1920.61  4665.9 1914.35    4705 1900.45    4719 1892.39  4724.3 1892.39
  4729.5 1887.81  4801.2 1860.36  4811.9 1858.08  4824.8 1862.72    4866 1861.43
  4894.4 1849.36  4899.5 1851.94    4930 1843.73  4930.5 1843.23  4941.3 1843.73
    4982 1844.27  4997.5 1847.68    5150 1850.26    5170 1854.01  5194.9 1862.91
    5210 1869.63    5220 1882.95    5230 1891.81    5270    1906    5300 1910.41
#Mann= 6 ,-1 , 0
  4365.6     .07       0  4604.5      .1       0  4801.2     .07       0
    4930     .05       0  4941.3     .07       0  5194.9      .1       0
Bank Sta=4930,4941.3
XS Rating Curve= 0 ,0
Exp/Cntr=0.3,0.1

Type RM Length L Ch R = 1 ,17717   ,483,483,483
BEGIN DESCRIPTION:
Tegner Creek 32.0
END DESCRIPTION:
XS GIS Cut Line= 4
      1862348.17      13925744.2      1862646.91     13925634.69
        1863025.       13925375.      1863125.03     13925324.99
#Sta/Elev= 30
  4218.6    1924  4286.7 1902.68  4335.3 1891.54  4385.6 1883.58  4464.4 1878.36
  4520.1 1870.62  4671.3 1864.33    4680  1866.3  4686.2 1871.74  4701.1 1870.68
  4707.2 1867.67  4728.6 1866.59    4737 1862.33    4758 1859.66  4922.7 1853.97
  4946.1 1848.47  4965.1 1847.37  4976.5 1843.46  4998.1 1841.76  4998.6 1841.26
  5009.6 1841.76  5031.8 1845.55  5040.2 1849.86  5048.6 1858.95  5054.2 1861.76
  5062.5 1889.48  5070.9 1896.17  5084.9 1901.27  5093.3 1907.05  5107.3 1909.71
#Mann= 5 ,-1 , 0
  4218.6      .1       0  4335.3     .07       0  4976.5      .1       0
  4998.1     .05       0  5009.6      .1       0
Bank Sta=4998.1,5009.6
XS Rating Curve= 0 ,0
Exp/Cntr=0.3,0.1

Type RM Length L Ch R = 1 ,17234   ,466,466,466
BEGIN DESCRIPTION:
Tegner Creek 31.0
END DESCRIPTION:
XS GIS Cut Line= 3
      1862427.55      13925820.9        1863125.       13925825.
      1863225.03       13925825.
#Sta/Elev= 30
  4302.5 1904.26    4320 1897.56    4350 1888.93    4370 1884.26    4420 1876.49
  4444.2  1874.8    4470 1872.63    4510 1866.04    4540 1863.35    4630 1859.94
    4670 1859.97    4730 1858.31    4790 1855.07    4830  1854.1    4880 1850.94
    4900 1849.01    4910  1846.8    4937  1844.5    4970 1841.89  4984.1  1839.5
  4984.6    1839  4995.8  1839.5    5010 1842.13    5030 1857.51    5040 1881.67
    5050 1897.34    5060  1899.8    5070  1900.6    5090 1899.53    5100 1900.12
#Mann= 5 ,-1 , 0
  4302.5      .1       0  4444.2     .07       0    4937      .1       0
  4984.1     .05       0  4995.8      .1       0
Bank Sta=4984.1,4995.8
XS Rating Curve= 0 ,0
Exp/Cntr=0.3,0.1

Type RM Length L Ch R = 1 ,16768   ,451,451,451
BEGIN DESCRIPTION:
Tegner Creek 30.0
END DESCRIPTION:
XS GIS Cut Line= 3
      1862767.84     13926548.86        1863075.       13926275.
      1863400.08     13925972.17
#Sta/Elev= 30
  4588.5 1920.72  4624.9 1919.39  4660.2  1908.2  4681.1    1894  4688.6 1892.62
  4695.3  1887.6  4702.8 1885.92  4709.5 1880.28    4717  1878.9  4723.7 1873.54
  4731.2 1872.28  4752.9  1860.9  4794.8 1850.66  4970.2 1837.45    4987  1836.3
  4987.5  1835.8  4998.8  1836.3  5028.1 1840.27  5035.4 1844.45  5042.3 1844.06
  5049.6 1848.29  5063.8 1850.53  5084.8 1849.49  5134.6 1854.07  5212.3 1854.88
  5219.1 1857.31  5239.1 1857.93  5303.3 1861.93  5403.3 1865.77  5444.3 1874.43
#Mann= 7 ,-1 , 0
  4588.5     .07       0  4752.9      .1       0  4970.2     .07       0
    4987     .05       0  4998.8     .07       0  5239.1    .035       0
  5303.3      .1       0
Bank Sta=4987,4998.8
XS Rating Curve= 0 ,0
Exp/Cntr=0.3,0.1

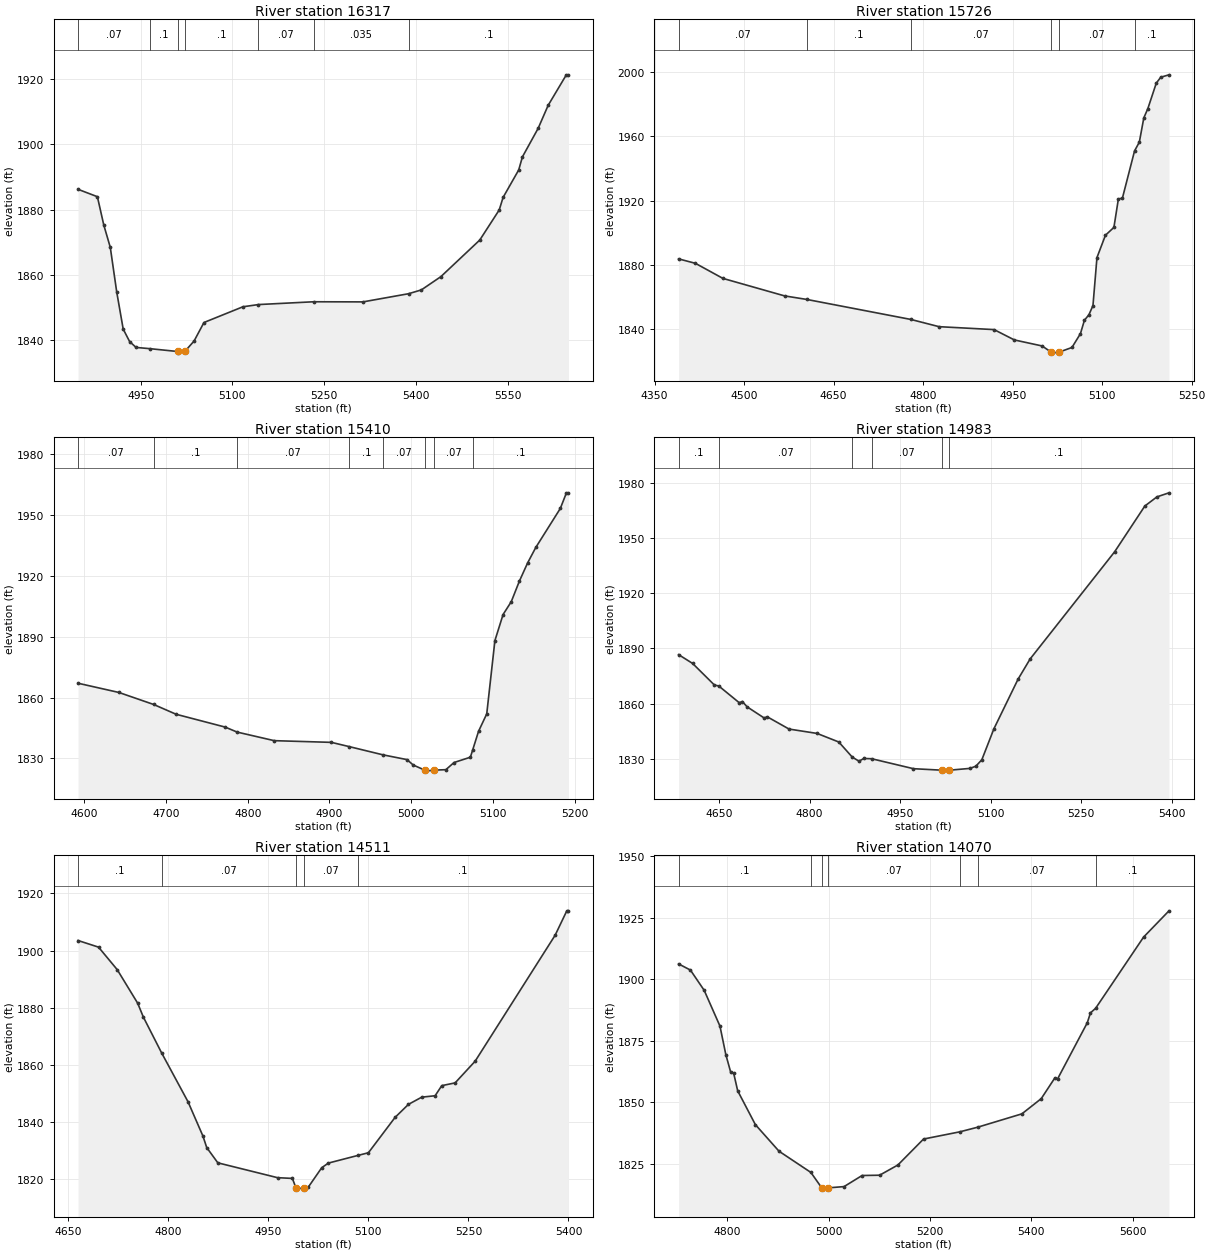
Type RM Length L Ch R = 1 ,16317   ,591,591,591
BEGIN DESCRIPTION:
Tegner Creek 29.0
END DESCRIPTION:
XS GIS Cut Line= 3
      1863275.01     13926624.98        1863325.       13926475.
      1863525.59     13925863.45
#Sta/Elev= 30
  4847.7 1886.22  4879.3 1883.95  4889.8 1875.22  4900.4 1868.39  4910.9 1854.69
  4921.5  1843.3    4932 1839.48  4942.5 1837.68  4965.1  1837.3  5010.4 1836.43
  5010.9 1835.93  5022.2 1836.43  5037.4 1839.66  5053.5 1845.33  5117.2 1850.16
  5142.6 1850.84  5233.1  1851.7  5313.4 1851.66    5388 1854.17  5408.9 1855.34
  5440.8 1859.41  5504.4 1870.65  5536.2 1879.89  5542.5 1883.73  5568.1 1892.19
  5574.1 1896.18  5599.9 1904.97  5616.2 1912.01  5645.9 1921.37  5649.4 1921.37
#Mann= 7 ,-1 , 0
  4847.7     .07       0  4965.1      .1       0  5010.4     .05       0
  5022.2      .1       0  5142.6     .07       0  5233.1    .035       0
    5388      .1       0
Bank Sta=5010.4,5022.2
XS Rating Curve= 0 ,0
Exp/Cntr=0.3,0.1

Type RM Length L Ch R = 1 ,15726   ,316,316,316
BEGIN DESCRIPTION:
Tegner Creek 28.0
END DESCRIPTION:
XS GIS Cut Line= 3
      1863313.38     13926671.27      1863860.85     13926421.76
      1864024.97     13926275.02
#Sta/Elev= 30
  4390.1 1883.76  4418.3 1880.99  4464.4  1871.6  4567.7 1860.71  4604.8 1858.51
  4779.5 1846.03  4826.6 1841.54  4918.8 1839.72  4952.8 1833.28  4999.2 1829.54
    5015 1825.57  5015.5 1825.07  5026.9 1825.57  5049.3  1828.6  5063.5 1837.18
  5070.2 1845.56  5077.7 1848.95  5084.5 1854.67  5091.2 1884.56  5105.4 1898.48
  5119.6 1903.35  5127.1  1921.1  5133.8 1921.52  5154.2 1950.99  5162.2 1956.44
  5169.7 1971.54  5176.4 1977.25  5190.6 1993.19  5198.1 1996.87  5211.9 1998.36
#Mann= 6 ,-1 , 0
  4390.1     .07       0  4604.8      .1       0  4779.5     .07       0
    5015     .05       0  5026.9     .07       0  5154.2      .1       0
Bank Sta=5015,5026.9
XS Rating Curve= 0 ,0
Exp/Cntr=0.3,0.1

Type RM Length L Ch R = 1 ,15410   ,427,427,427
BEGIN DESCRIPTION:
Tegner Creek 27.0
END DESCRIPTION:
XS GIS Cut Line= 3
      1863424.96       13926675.        1863825.       13926675.
      1864024.96       13926675.
#Sta/Elev= 30
  4592.4  1867.1  4642.4 1862.55  4684.9 1856.63  4712.4  1851.8  4772.4 1845.48
    4787 1843.02  4832.4 1838.79  4902.4 1837.95  4924.3 1835.84  4965.7 1831.78
  4994.9 1829.44  5002.4 1826.79  5016.5 1824.27    5017 1823.77  5028.4 1824.27
  5042.4 1824.48  5052.4 1828.02  5072.4 1830.63  5075.3 1834.34  5082.4 1843.43
  5092.4 1851.99  5102.4 1888.15  5112.4 1900.99  5122.4 1907.31  5132.4  1917.5
  5142.4 1926.41  5152.4 1934.04  5182.4 1953.26  5189.9 1960.98  5192.4 1960.98
#Mann= 8 ,-1 , 0
  4592.4     .07       0  4684.9      .1       0    4787     .07       0
  4924.3      .1       0  4965.7     .07       0  5016.5     .05       0
  5028.4     .07       0  5075.3      .1       0
Bank Sta=5016.5,5028.4
XS Rating Curve= 0 ,0
Exp/Cntr=0.3,0.1

Type RM Length L Ch R = 1 ,14983   ,472,472,472
BEGIN DESCRIPTION:
Tegner Creek 26.0
END DESCRIPTION:
XS GIS Cut Line= 3
      1863274.99       13927125.        1863675.       13927025.
      1864074.98       13927025.
#Sta/Elev= 30
  4582.9 1886.68  4606.1  1881.9  4642.2 1870.19  4649.5 1869.65  4683.4 1860.57
  4688.6 1861.23  4696.3 1858.37  4724.6  1852.3  4729.8 1852.93  4765.9 1846.28
  4812.3 1843.91  4848.3 1839.25  4870.6 1831.05  4881.8 1828.84  4889.6 1830.31
  4902.6 1830.18    4972 1824.77  5019.3 1823.95  5019.8 1823.45  5031.2 1823.95
  5065.2 1824.92  5075.2 1826.09  5085.2 1829.62  5105.2 1846.42  5145.2 1873.35
  5165.2 1884.33  5305.2 1942.49  5355.2 1967.32  5375.2 1972.28  5395.2 1974.48
#Mann= 6 ,-1 , 0
  4582.9      .1       0  4649.5     .07       0  4870.6      .1       0
  4902.6     .07       0  5019.3     .05       0  5031.2      .1       0
Bank Sta=5019.3,5031.2
XS Rating Curve= 0 ,0
Exp/Cntr=0.3,0.1

Type RM Length L Ch R = 1 ,14511   ,441,441,441
BEGIN DESCRIPTION:
Tegner Creek 25.0
END DESCRIPTION:
XS GIS Cut Line= 3
        1863175.       13927275.        1863475.       13927425.
      1863874.99       13927425.
#Sta/Elev= 30
  4664.6  1903.5  4695.3 1901.18  4723.3 1893.31    4754 1881.56  4762.4 1876.76
  4789.8 1864.21  4829.5 1847.06  4851.9 1835.04  4857.5 1831.05  4874.2 1825.69
  4963.7  1820.5    4986 1820.24  4991.2 1816.99  4991.7 1816.49  5003.2 1816.99
    5010 1817.24    5030 1823.99    5040 1825.61    5084 1828.27    5100 1829.22
    5140  1841.6    5160 1846.15    5180 1848.68    5200 1849.17    5210 1852.71
    5230 1853.67    5260 1861.25    5380 1905.35  5397.5 1913.89    5400 1913.89
#Mann= 5 ,-1 , 0
  4664.6      .1       0  4789.8     .07       0  4991.2     .05       0
  5003.2     .07       0    5084      .1       0
Bank Sta=4991.2,5003.2
XS Rating Curve= 0 ,0
Exp/Cntr=0.3,0.1

Type RM Length L Ch R = 1 ,14070   ,447,447,447
BEGIN DESCRIPTION:
Tegner Creek 24.0
END DESCRIPTION:
XS GIS Cut Line= 3
      1862974.97     13927624.98        1863225.       13927775.
      1863894.63     13927872.04
#Sta/Elev= 30
  4703.7 1906.22  4727.1 1903.71  4754.3 1895.46  4785.4 1880.92    4797 1869.32
  4806.7  1862.1  4812.6 1861.65  4820.4  1854.6  4855.3 1840.85    4902 1830.03
  4964.9  1821.4  4986.4 1815.11  4986.9 1814.61  4998.4 1815.11  5030.4 1815.64
    5066 1820.15  5100.6 1820.27  5136.7 1824.43  5187.3 1834.98  5258.8 1837.91
  5293.9 1839.78  5381.5 1845.23  5419.7 1851.42  5446.7 1859.89  5451.8 1859.39
  5510.6 1882.28  5516.9 1886.31    5527 1888.15  5621.8 1917.14  5671.9 1927.81
#Mann= 7 ,-1 , 0
  4703.7      .1       0  4964.9     .07       0  4986.4     .05       0
  4998.4     .07       0  5258.8      .1       0  5293.9     .07       0
    5527      .1       0
Bank Sta=4986.4,4998.4
XS Rating Curve= 0 ,0
Exp/Cntr=0.3,0.1

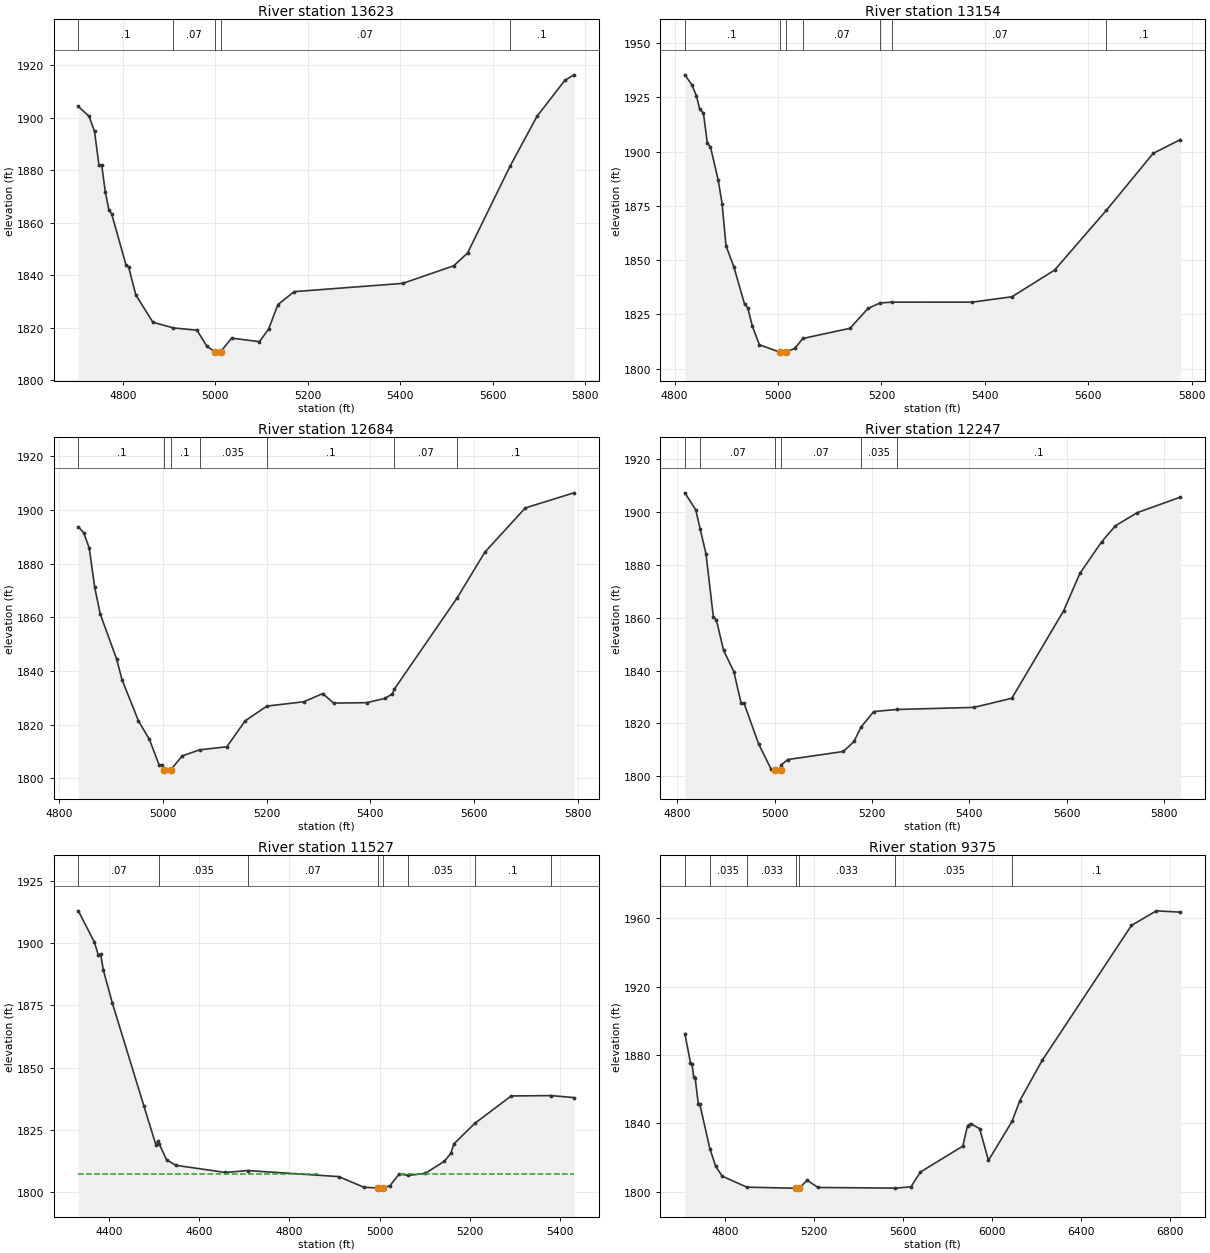
Type RM Length L Ch R = 1 ,13623   ,469,469,469
BEGIN DESCRIPTION:
Tegner Creek 23.0
END DESCRIPTION:
XS GIS Cut Line= 3
      1862824.99     13928024.99        1863075.       13928175.
      1863855.02     13928152.74
#Sta/Elev= 30
  4703.8  1904.3  4727.1 1900.55  4738.8 1894.81  4748.5 1881.93  4754.3 1882.09
  4762.1  1871.8  4769.9 1864.94  4775.7 1863.49  4806.8    1844  4812.7    1843
  4828.2 1832.46  4865.1 1822.08  4909.2 1819.93  4960.4 1819.04  4981.8 1812.94
  4999.3 1810.81  4999.8 1810.31  5011.4 1810.81  5035.4 1816.02  5095.4 1814.68
  5115.4 1819.48  5135.4 1828.79  5170.5 1833.74  5405.5 1836.89  5515.6 1843.59
  5545.6 1848.45  5637.3 1881.48  5695.6  1900.5  5755.7  1914.2  5775.7 1916.36
#Mann= 5 ,-1 , 0
  4703.8      .1       0  4909.2     .07       0  4999.3     .05       0
  5011.4     .07       0  5637.3      .1       0
Bank Sta=4999.3,5011.4
XS Rating Curve= 0 ,0
Exp/Cntr=0.3,0.1

Type RM Length L Ch R = 1 ,13154   ,470,470,470
BEGIN DESCRIPTION:
Tegner Creek 22.0
END DESCRIPTION:
XS GIS Cut Line= 3
      1862975.04     13928724.97        1863125.       13928625.
      1863843.79     13928326.07
#Sta/Elev= 30
  4819.8 1935.39  4833.3 1930.82  4842.3 1925.66  4848.3 1919.87  4855.8 1917.61
  4863.3 1903.91  4869.3 1902.23  4884.4  1886.8  4891.9 1875.95  4899.4 1856.62
  4914.4 1847.05  4935.4 1829.67  4941.4 1828.07  4950.5 1819.48    4964 1811.01
  5003.1 1807.65  5003.6 1807.15  5015.3 1807.65  5032.5 1809.35    5048  1813.9
  5139.3  1818.6    5174 1827.72  5197.1 1830.26  5221.4 1830.66  5375.7 1830.65
  5452.6 1833.13    5535 1845.43  5635.3 1873.01  5725.7 1899.21  5778.5 1905.56
#Mann= 7 ,-1 , 0
  4819.8      .1       0  5003.1     .05       0  5015.3      .1       0
    5048     .07       0  5197.1      .1       0  5221.4     .07       0
  5635.3      .1       0
Bank Sta=5003.1,5015.3
XS Rating Curve= 0 ,0
Exp/Cntr=0.3,0.1

Type RM Length L Ch R = 1 ,12684   ,437,437,437
BEGIN DESCRIPTION:
Tegner Creek 21.0
END DESCRIPTION:
XS GIS Cut Line= 3
        1863375.       13929125.        1863425.       13928975.
      1863937.23     13928364.67
#Sta/Elev= 30
  4837.3 1893.71  4847.8 1891.42  4858.4 1885.72  4868.9 1871.09  4879.5 1861.22
  4911.1 1844.41  4921.6 1836.68  4953.2  1821.4  4974.3 1814.48  4992.8 1805.06
  4998.7 1805.06    5003 1803.19  5003.5 1802.69  5015.2 1803.19  5037.7 1808.37
    5071 1810.62  5123.5 1811.77  5158.7 1821.41  5200.5 1826.91  5271.9 1828.53
  5308.3 1831.58  5329.1 1828.03  5392.8 1828.18    5428 1829.77  5442.3 1831.46
  5446.1 1833.22    5567 1867.17  5620.5 1884.23  5698.5 1900.72  5792.2 1906.34
#Mann= 7 ,-1 , 0
  4837.3      .1       0    5003     .05       0  5015.2      .1       0
    5071    .035       0  5200.5      .1       0  5446.1     .07       0
    5567      .1       0
Bank Sta=5003,5015.2
XS Rating Curve= 0 ,0
Exp/Cntr=0.3,0.1

Type RM Length L Ch R = 1 ,12247   ,720,720,720
BEGIN DESCRIPTION:
Tegner Creek 20.0
END DESCRIPTION:
XS GIS Cut Line= 3
      1863675.01     13929324.99        1863775.       13929175.
      1864006.34     13928369.22
#Sta/Elev= 30
  4815.5 1907.35    4838 1900.86  4847.1 1893.56  4859.1 1884.06  4874.1 1860.27
  4880.1  1859.3  4895.1 1847.65  4916.1 1839.62  4931.2 1827.58  4937.2 1827.57
  4967.2 1812.15  4992.8 1802.61    5000 1802.36  5000.5 1801.86  5012.3 1802.36
  5012.6 1804.08    5027 1806.25  5141.4 1809.31  5163.1  1813.1  5177.5 1818.54
  5203.8 1824.46  5251.7 1825.23  5409.6 1826.02  5487.5 1829.48  5593.8 1862.58
  5627.6  1876.9    5672 1888.75  5700.2 1894.84  5744.9 1899.81  5834.1 1905.73
#Mann= 6 ,-1 , 0
  4815.5      .1       0  4847.1     .07       0    5000     .05       0
  5012.3     .07       0  5177.5    .035       0  5251.7      .1       0
Bank Sta=5000,5012.3
XS Rating Curve= 0 ,0
Exp/Cntr=0.3,0.1

Type RM Length L Ch R = 1 ,11527   ,2152,2152,2152
BEGIN DESCRIPTION:
Tegner Creek 19.0
END DESCRIPTION:
XS GIS Cut Line= 3
      1863789.76     13929393.88      1864358.76     13929348.22
      1864764.45     13929008.77
#Sta/Elev= 30
  4331.4 1912.85  4366.8 1900.37  4375.9 1895.12  4380.9 1895.58  4386.8  1889.2
  4406.9 1875.86  4477.1 1834.52  4503.6    1819  4508.6 1820.54  4510.6  1819.5
  4527.3 1813.03  4547.3 1810.84  4657.7 1807.95  4707.4 1808.72  4909.4 1806.29
  4965.4 1801.99  4995.5 1801.77    4996 1801.27  5007.8 1801.77  5022.7 1802.61
  5043.5 1807.35  5063.7 1806.76  5100.7 1807.56  5143.7 1812.43    5158 1815.61
  5164.5 1819.35  5211.3 1827.66    5292 1838.63  5380.9 1838.77  5431.2 1837.97
#Mann= 8 ,-1 , 0
  4331.4     .07       0  4510.6    .035       0  4707.4     .07       0
  4995.5     .05       0  5007.8     .07       0  5063.7    .035       0
  5211.3      .1       0  5380.9     .07       0
#XS Ineff= 2 , 0
         4865.73 1807.43 5044.33         1807.46
Permanent Ineff=
       F       F
Bank Sta=4995.5,5007.8
XS Rating Curve= 0 ,0
Exp/Cntr=0.3,0.1

Type RM Length L Ch R = 1 ,9375    ,270,270,270
BEGIN DESCRIPTION:
Tegner Creek 17.1
END DESCRIPTION:
XS GIS Cut Line= 6
      1863813.55     13929501.52       1864062.2     13929700.43
      1864245.08     13929881.69       1864762.6     13930349.55
      1865365.67     13930415.03      1865702.04     13930319.72
#Sta/Elev= 30
  4619.1 1892.45  4644.4 1875.55  4650.8 1874.99  4658.8  1867.3  4665.2 1866.77
  4679.6 1851.44    4686 1851.35  4731.6 1825.21  4758.1 1814.73  4786.9  1809.1
  4898.1 1802.62    5120 1801.97  5120.5 1801.47  5133.1 1801.97    5169 1806.65
  5218.7 1802.44  5566.8 1802.06  5636.4  1802.8    5679  1811.5  5869.6 1826.64
  5890.9 1838.65  5905.1 1839.84  5945.4 1836.85    5985 1818.27  6091.2 1841.14
  6126.4 1853.31    6227 1876.87  6628.2 1955.78  6740.3 1964.34  6848.9 1963.57
#Mann= 7 ,-1 , 0
  4619.1      .1       0  4731.6    .035       0  4898.1    .033       0
    5120    .033       0  5133.1    .033       0  5566.8    .035       0
  6091.2      .1       0
Bank Sta=5120,5133.1
XS Rating Curve= 0 ,0
Exp/Cntr=0.3,0.1

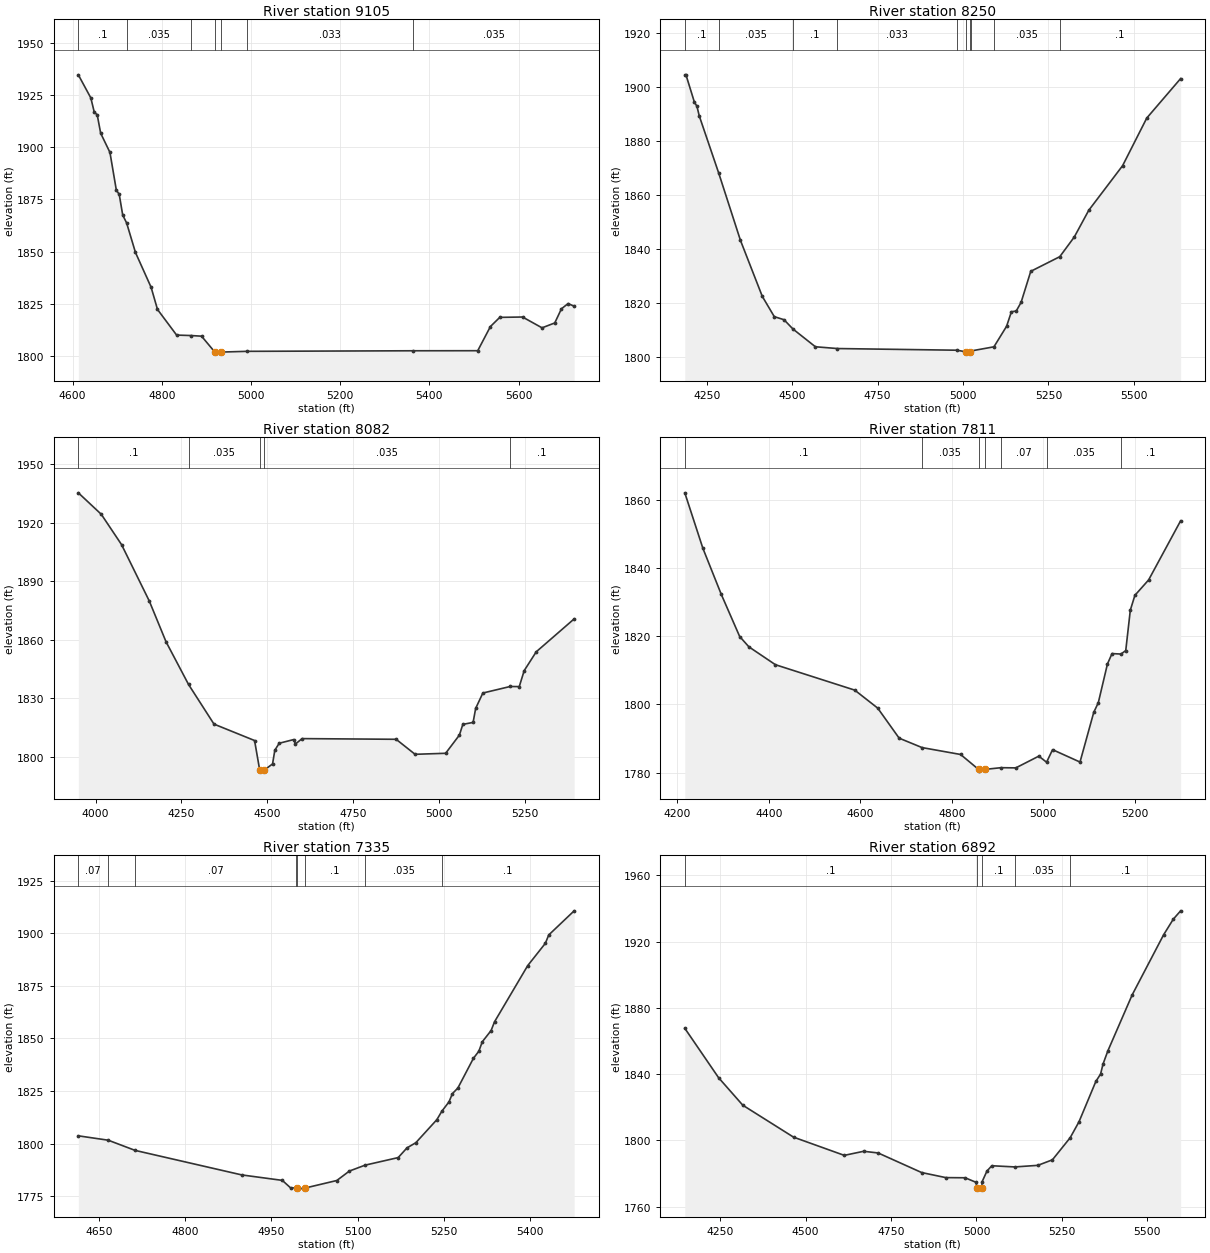
Type RM Length L Ch R = 1 ,9105    ,855,855,855
BEGIN DESCRIPTION:
Tegner Creek 18.0
END DESCRIPTION:
XS GIS Cut Line= 3
      1863724.98     13929674.98       1864009.1     13929915.17
      1864624.97     13930324.98
#Sta/Elev= 30
  4612.8 1934.65  4640.8 1923.59  4648.6 1916.71  4655.1 1915.53  4662.9 1906.68
  4683.7 1897.47    4698 1879.43  4704.5 1877.38  4712.3 1867.48  4721.1 1863.68
  4740.9 1849.56    4776 1832.87  4790.3 1822.26  4833.2 1809.98  4865.8 1809.76
  4889.1 1809.46  4918.9 1801.84  4919.4 1801.34    4932 1801.84    4991  1802.2
    5363 1802.47  5508.4  1802.5  5536.8 1814.07  5557.8 1818.47  5608.9 1818.64
  5652.6 1813.46  5681.1  1815.8  5696.1 1822.58  5711.1 1825.09  5724.6 1823.79
#Mann= 7 ,-1 , 0
  4612.8      .1       0  4721.1    .035       0  4865.8      .1       0
  4918.9    .033       0    4932      .1       0    4991    .033       0
    5363    .035       0
#XS Ineff= 2 , 0
                         5569.83         1818.44
Permanent Ineff=
       F       F
Bank Sta=4918.9,4932
XS Rating Curve= 0 ,0
Exp/Cntr=0.3,0.1

Type RM Length L Ch R = 1 ,8250    ,168,168,168
BEGIN DESCRIPTION:
Tegner Creek 17.0
END DESCRIPTION:
XS GIS Cut Line= 3
      1863574.97     13929974.97        1864175.       13930525.
      1864625.02     13930975.02
#Sta/Elev= 30
  4186.1 1904.49  4189.5 1904.49  4214.2 1894.35  4221.6 1892.84  4228.4 1889.26
  4285.3 1868.06  4348.9 1843.11  4412.8 1822.34  4447.9 1814.82  4476.3 1813.69
  4502.6 1810.23  4568.1 1803.66  4632.5    1803  4982.1 1802.38  5007.7  1801.8
  5008.2  1801.3  5020.8  1801.8  5023.1  1802.1  5090.4 1803.64  5127.4 1811.25
  5141.5 1816.64  5155.6 1816.91  5169.8 1820.11  5198.1 1831.63    5283 1837.06
  5325.4 1844.35  5367.8 1854.27  5466.8 1870.81  5537.5 1888.47  5636.5  1903.1
#Mann= 10 ,-1 , 0
  4186.1      .1       0  4285.3    .035       0  4502.6      .1       0
  4632.5    .033       0  4982.1    .035       0  5007.7    .035       0
  5020.8    .035       0  5023.1    .033       0  5090.4    .035       0
    5283      .1       0
Bank Sta=5007.7,5020.8
XS Rating Curve= 0 ,0
Exp/Cntr=0.3,0.1

Type RM Length L Ch R = 1 ,8082    ,271,271,271
BEGIN DESCRIPTION:
Tegner Creek 16.1
END DESCRIPTION:
XS GIS Cut Line= 5
      1863223.52       13930236.      1863733.52     13930526.84
      1864131.65     13930658.91      1864252.99     13930666.02
      1864488.19     13930877.49
#Sta/Elev= 30
  3949.6  1935.3  4016.4 1924.31  4075.5 1908.76  4156.2 1879.91  4205.1 1858.99
  4270.7  1837.1  4344.8  1816.8    4463 1808.39    4478 1793.21  4478.5 1792.71
  4491.1 1793.21  4515.4  1796.4    4522 1803.41  4534.7 1806.99  4576.8 1808.87
  4582.1 1806.62  4601.5 1809.37  4875.4 1809.02  4930.6 1801.33  5019.6 1801.85
  5059.7 1811.18  5069.7 1816.67  5099.6 1817.67  5107.1 1824.86    5128 1832.72
  5207.5 1836.07  5234.1 1836.02  5248.4 1844.19  5283.5 1853.84    5394 1870.71
#Mann= 5 ,-1 , 0
  3949.6      .1       0  4270.7    .035       0    4478    .035       0
  4491.1    .035       0  5207.5      .1       0
Bank Sta=4478,4491.1
XS Rating Curve= 0 ,0
Exp/Cntr=0.3,0.1

Type RM Length L Ch R = 1 ,7811    ,476,476,476
BEGIN DESCRIPTION:
Tegner Creek 16.0
END DESCRIPTION:
XS GIS Cut Line= 3
      1863295.71     13930962.42        1864075.       13930875.
      1864375.02       13930875.
#Sta/Elev= 30
  4216.4 1862.03  4255.9 1845.79  4296.2 1832.26  4336.4 1819.92  4356.6 1816.89
  4414.7 1811.65    4588 1804.21  4638.3 1798.93  4685.1 1790.13  4735.2 1787.37
  4819.5 1785.35  4858.8 1780.97  4859.3 1780.47    4872 1780.97    4908 1781.48
  4940.2 1781.42  4990.5 1784.86  5007.5 1783.08  5020.6 1786.76  5080.6 1783.13
  5110.6 1797.68  5120.6 1800.53  5140.6 1811.88  5150.6 1814.92  5170.1 1814.78
  5180.6  1815.8  5190.6 1827.64  5200.6 1831.99  5230.6  1836.5  5300.6 1853.83
#Mann= 7 ,-1 , 0
  4216.4      .1       0  4735.2    .035       0  4858.8     .05       0
    4872    .035       0    4908     .07       0  5007.5    .035       0
  5170.1      .1       0
Bank Sta=4858.8,4872
XS Rating Curve= 0 ,0
Exp/Cntr=0.3,0.1

Type RM Length L Ch R = 1 ,7335    ,443,443,443
BEGIN DESCRIPTION:
Tegner Creek 15.0
END DESCRIPTION:
XS GIS Cut Line= 3
        1863975.       13931525.        1864275.       13931275.
      1864674.99     13931025.01
#Sta/Elev= 30
  4614.1 1803.74  4666.1 1801.66  4712.8 1796.82  4898.5 1785.15  4968.8 1782.57
  4983.1 1779.03  4992.8 1778.95  4994.7 1778.91  4995.2 1778.41  5008.1 1778.91
  5063.6 1782.51  5085.4 1786.99  5112.6 1789.79  5170.3  1793.4  5185.6 1798.01
    5201 1800.47  5237.5 1811.41  5246.4  1815.5  5258.7  1819.9  5264.6 1823.79
  5274.1 1826.47  5301.2 1840.61  5310.6 1843.97  5316.5 1848.42  5331.9 1853.79
  5337.8 1857.92  5395.5 1884.62  5426.2 1895.23  5432.1  1899.2  5476.3 1910.67
#Mann= 8 ,-1 , 0
  4614.1     .07       0  4666.1      .1       0  4712.8     .07       0
  4992.8      .1       0  4994.7     .05       0  5008.1      .1       0
  5112.6    .035       0  5246.4      .1       0
Bank Sta=4994.7,5008.1
XS Rating Curve= 0 ,0
Exp/Cntr=0.3,0.1

Type RM Length L Ch R = 1 ,6892    ,450,450,450
BEGIN DESCRIPTION:
Tegner Creek 14.0
END DESCRIPTION:
XS GIS Cut Line= 3
      1863925.03     13932224.97        1864525.       13931625.
      1864975.03     13931224.97
#Sta/Elev= 30
  4146.6 1867.68  4245.5 1837.81  4316.3  1821.2  4464.8  1801.9  4613.2  1790.9
  4669.8 1793.36  4712.2 1792.35  4839.5 1780.52  4910.2 1777.46  4966.8 1777.36
  4998.4 1774.64  5002.1    1771  5002.6  1770.5  5015.6    1771  5016.4 1774.96
  5030.6 1781.43  5044.8 1784.63  5112.3 1783.91  5179.5 1784.87  5222.1 1788.21
  5274.1 1801.57  5299.9  1811.2  5349.2 1835.58    5363 1840.01  5370.1 1846.01
  5384.3 1854.03  5455.4 1887.84  5547.4 1924.16  5575.8 1933.62  5597.2 1938.65
#Mann= 5 ,-1 , 0
  4146.6      .1       0  5002.1     .05       0  5015.6      .1       0
  5112.3    .035       0  5274.1      .1       0
Bank Sta=5002.1,5015.6
XS Rating Curve= 0 ,0
Exp/Cntr=0.3,0.1