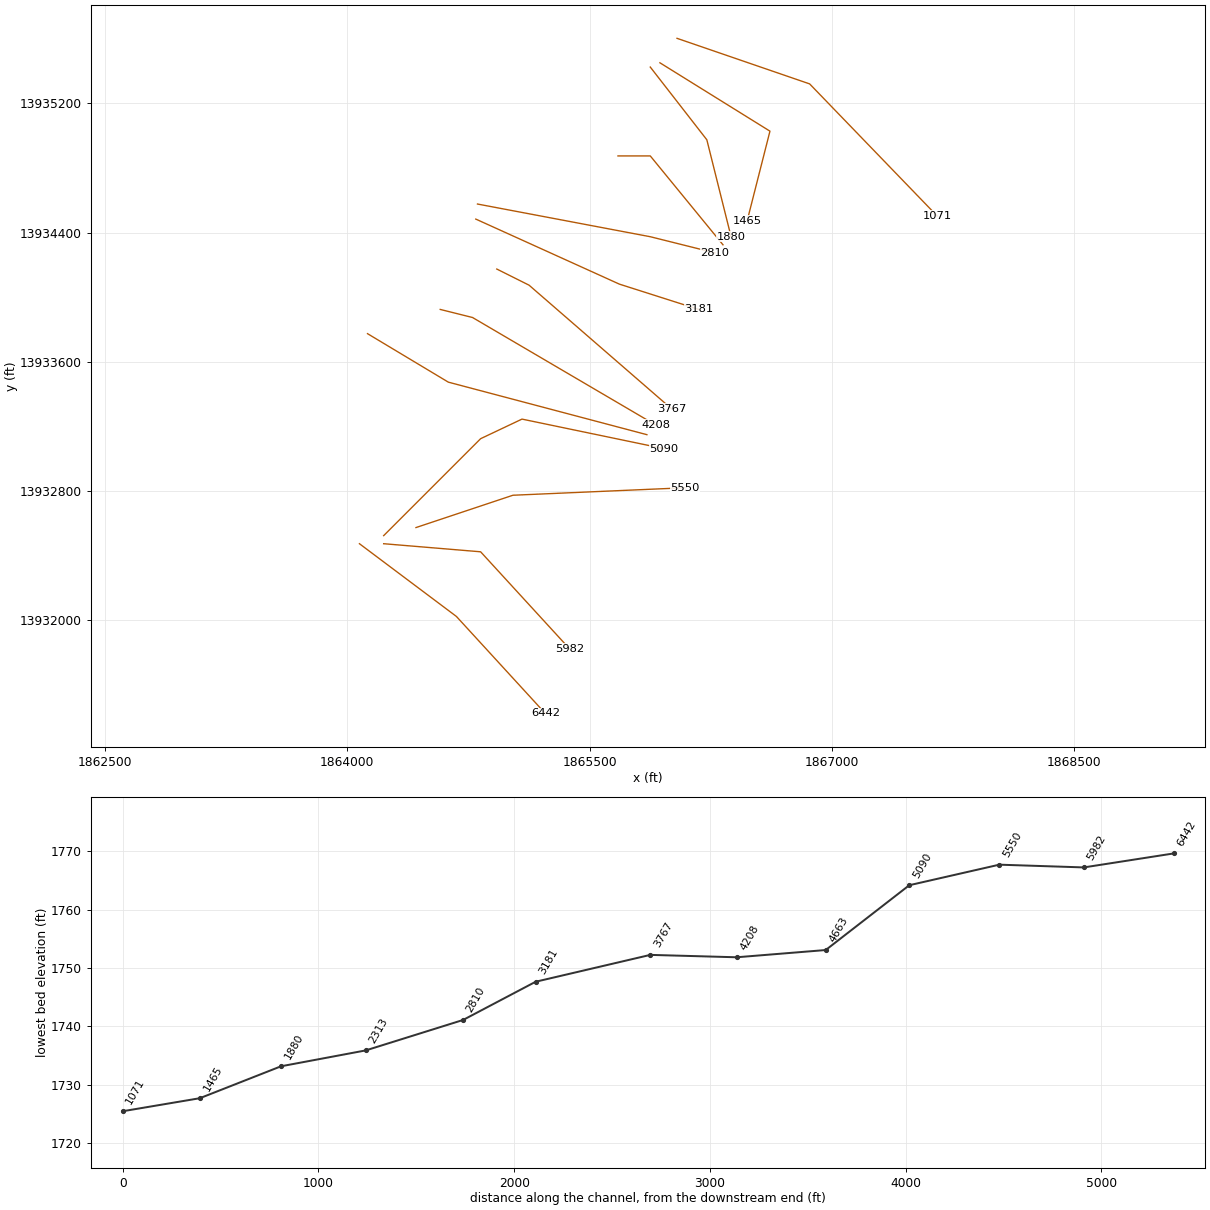
HEC-RAS study Tegener Creek.prj: Tegener Creek Base Level Engineering

--- Tegener Creek.g01 (geometry) --- (continued)

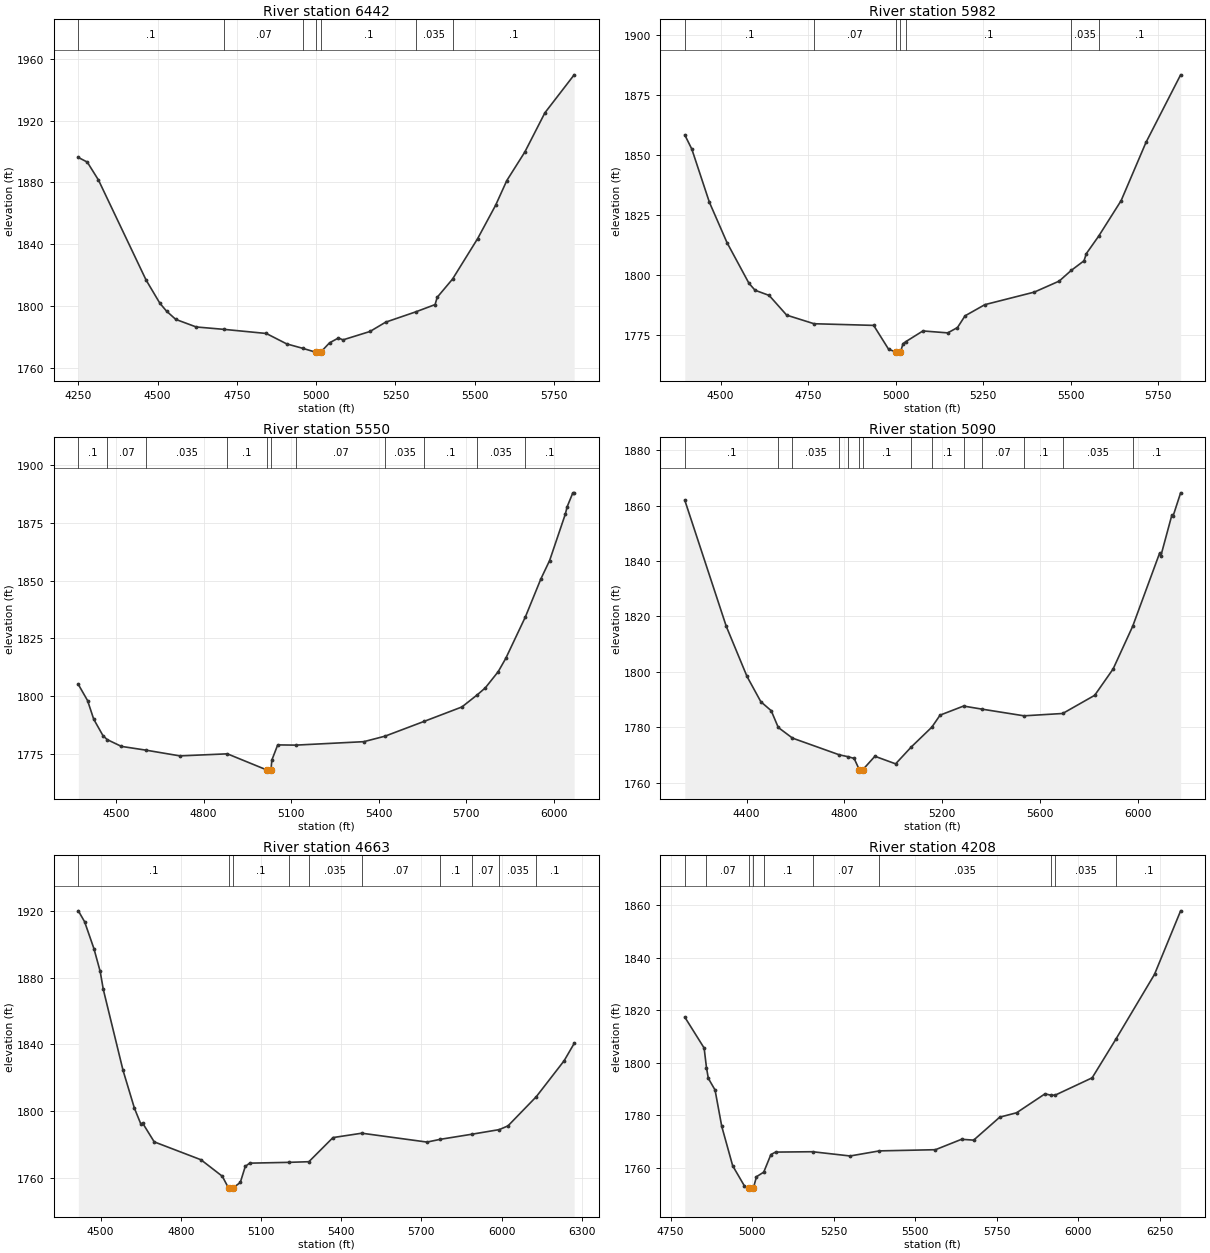
Type RM Length L Ch R = 1 ,6442    ,460,460,460
BEGIN DESCRIPTION:
Tegner Creek 13.0
END DESCRIPTION:
XS GIS Cut Line= 3
      1864074.96     13932475.03        1864675.       13932025.
      1865225.01     13931424.99
#Sta/Elev= 30
  4249.9  1896.2  4278.1  1893.2  4313.5 1881.56  4463.5 1816.94  4507.2 1801.86
  4528.1  1796.8  4557.2 1791.45  4621.8 1786.54  4709.5 1784.99  4842.7 1782.34
  4907.2 1775.59  4959.1 1772.65  5000.3 1770.12  5000.8 1769.62  5013.8 1770.12
  5042.2 1776.27  5070.5 1779.42  5084.7  1778.2  5169.8 1783.62  5219.2 1789.64
  5315.1 1796.38  5375.2 1801.02  5381.9 1805.73  5430.3 1817.53  5509.6 1843.75
  5566.3 1865.35  5601.5 1881.28  5658.2 1899.68  5721.7 1925.11  5813.9 1949.65
#Mann= 7 ,-1 , 0
  4249.9      .1       0  4709.5     .07       0  4959.1      .1       0
  5000.3     .05       0  5013.8      .1       0  5315.1    .035       0
  5430.3      .1       0
Bank Sta=5000.3,5013.8
XS Rating Curve= 0 ,0
Exp/Cntr=0.3,0.1

Type RM Length L Ch R = 1 ,5982    ,432,432,432
BEGIN DESCRIPTION:
Tegner Creek 12.0
END DESCRIPTION:
XS GIS Cut Line= 3
      1864224.96       13932475.        1864825.       13932425.
      1865375.02     13931824.97
#Sta/Elev= 30
  4397.9 1858.38    4418 1852.44  4468.2 1830.23  4518.4 1813.41  4581.1 1796.41
  4598.6 1793.49  4638.8 1791.33  4688.9 1783.09    4767  1779.5  4937.3 1778.81
    4980 1768.83  5000.3 1767.72  5000.8 1767.22  5013.9 1767.72  5021.3 1771.19
  5029.1 1772.02    5078 1776.49  5148.9 1775.68  5176.7 1777.91  5198.3  1782.8
    5255 1787.48  5396.2 1792.72  5467.1 1797.31  5501.3 1801.75    5538 1805.79
  5544.8 1808.82  5579.9 1816.09  5644.1 1830.94    5715 1855.24    5814 1883.49
#Mann= 7 ,-1 , 0
  4397.9      .1       0    4767     .07       0  5000.3     .05       0
  5013.9     .07       0  5029.1      .1       0  5501.3    .035       0
  5579.9      .1       0
Bank Sta=5000.3,5013.9
XS Rating Curve= 0 ,0
Exp/Cntr=0.3,0.1

Type RM Length L Ch R = 1 ,5550    ,460,460,460
BEGIN DESCRIPTION:
Tegner Creek 11.0
END DESCRIPTION:
XS GIS Cut Line= 3
      1864425.03     13932575.01        1865025.       13932775.
      1866088.96     13932821.37
#Sta/Elev= 30
  4371.4 1805.13    4403 1798.16  4424.1 1790.11  4455.7 1783.03  4470.3  1781.3
  4518.9 1778.37  4601.4 1776.78  4719.2 1774.27  4881.6 1775.16  5016.8 1768.19
  5017.3 1767.69  5030.8 1768.19  5033.9 1772.46  5053.9 1779.02  5115.9 1778.92
  5348.7 1780.41  5421.4 1782.79  5556.4 1789.23  5684.5  1795.4  5736.4 1800.57
  5764.5 1803.63  5808.6 1810.61  5834.6 1816.37  5901.9 1834.32  5954.7 1850.66
  5984.8 1858.65  6038.6  1878.7  6044.8 1881.87  6064.3 1887.88  6068.8 1887.88
#Mann= 11 ,-1 , 0
  4371.4      .1       0  4470.3     .07       0  4601.4    .035       0
  4881.6      .1       0  5016.8     .05       0  5030.8      .1       0
  5115.9     .07       0  5421.4    .035       0  5556.4      .1       0
  5736.4    .035       0  5901.9      .1       0
Bank Sta=5016.8,5030.8
XS Rating Curve= 0 ,0
Exp/Cntr=0.3,0.1

Type RM Length L Ch R = 1 ,5090    ,427,427,427
BEGIN DESCRIPTION:
Tegner Creek 10.0
END DESCRIPTION:
XS GIS Cut Line= 4
      1864224.97     13932524.97        1864825.       13933125.
      1865081.08     13933246.27      1865959.34     13933063.47
#Sta/Elev= 30
  4147.1 1861.92  4316.9  1816.4  4401.7 1798.34  4458.3 1789.21  4500.7 1785.98
  4529.6 1779.93  4587.7 1776.09  4778.8 1770.07  4816.6 1769.34  4840.1 1768.75
  4861.3 1764.67  4861.8 1764.17  4875.4 1764.67    4925 1769.53  5009.8  1766.8
  5073.6 1772.86  5157.9 1780.03  5191.8 1784.38  5287.9 1787.65  5363.2 1786.54
  5535.2 1784.13  5693.5 1784.97  5824.4 1791.53  5899.8 1801.03  5979.8 1816.42
  6089.9 1842.79    6095  1841.8    6140 1856.49  6145.1 1856.17  6176.1  1864.6
#Mann= 14 ,-1 , 0
  4147.1      .1       0  4529.6     .07       0  4587.7    .035       0
  4778.8     .07       0  4816.6      .1       0  4861.3     .05       0
  4875.4      .1       0  5073.6     .07       0  5157.9      .1       0
  5287.9    .035       0  5363.2     .07       0  5535.2      .1       0
  5693.5    .035       0  5979.8      .1       0
Bank Sta=4861.3,4875.4
XS Rating Curve= 0 ,0
Exp/Cntr=0.3,0.1

Type RM Length L Ch R = 1 ,4663    ,455,455,455
BEGIN DESCRIPTION:
Tegner Creek 9.0
END DESCRIPTION:
XS GIS Cut Line= 3
      1864124.97     13933775.02        1864625.       13933475.
      1865854.19     13933149.82
#Sta/Elev= 30
    4417 1920.23  4440.4  1913.7  4475.3 1897.54  4498.7 1883.85  4510.3 1873.08
  4584.2 1824.41  4626.9 1801.63  4650.3 1792.37    4658 1792.59  4700.8 1781.46
  4875.7 1770.71  4955.4 1760.82  4979.4 1753.57  4979.9 1753.07  4993.7 1753.57
  5022.8 1757.06  5041.5 1766.74  5057.9 1768.67  5205.2 1769.16  5279.4 1769.54
  5369.5 1784.03  5477.3 1786.66  5721.3 1781.33  5771.3    1783  5888.7 1786.04
  5991.6 1788.82  6024.2 1791.08  6130.1 1808.62    6234 1830.17  6271.6 1840.57
#Mann= 10 ,-1 , 0
    4417      .1       0  4979.4     .05       0  4993.7      .1       0
  5205.2     .07       0  5279.4    .035       0  5477.3     .07       0
  5771.3      .1       0  5888.7     .07       0  5991.6    .035       0
  6130.1      .1       0
Bank Sta=4979.4,4993.7
XS Rating Curve= 0 ,0
Exp/Cntr=0.3,0.1

Type RM Length L Ch R = 1 ,4208    ,441,441,441
BEGIN DESCRIPTION:
Tegner Creek 8.0
END DESCRIPTION:
XS GIS Cut Line= 3
        1864575.       13933925.        1864775.       13933875.
      1865909.08     13933209.45
#Sta/Elev= 30
  4793.7 1817.41    4853 1805.63  4860.2 1798.15  4865.9 1794.06  4886.5 1789.63
  4907.1 1775.74  4940.6 1760.73  4976.7 1753.03  4990.1 1752.33  4990.6 1751.83
  5004.4 1752.33  5013.5 1756.56  5035.9 1758.31  5057.8 1765.01  5072.1 1765.95
  5185.6 1766.09  5300.8 1764.47  5390.6 1766.41  5562.6 1766.86  5642.7 1770.83
  5679.8 1770.51  5759.9 1779.27  5811.5 1780.94  5898.6 1788.15    5918 1787.62
  5930.4 1787.69  6043.4 1794.27  6117.2 1809.22  6234.7 1833.72  6314.8 1857.94
#Mann= 10 ,-1 , 0
  4793.7      .1       0  4860.2     .07       0  4990.1     .05       0
  5004.4     .07       0  5035.9      .1       0  5185.6     .07       0
  5390.6    .035       0    5918      .1       0  5930.4    .035       0
  6117.2      .1       0
Bank Sta=4990.1,5004.4
XS Rating Curve= 0 ,0
Exp/Cntr=0.3,0.1

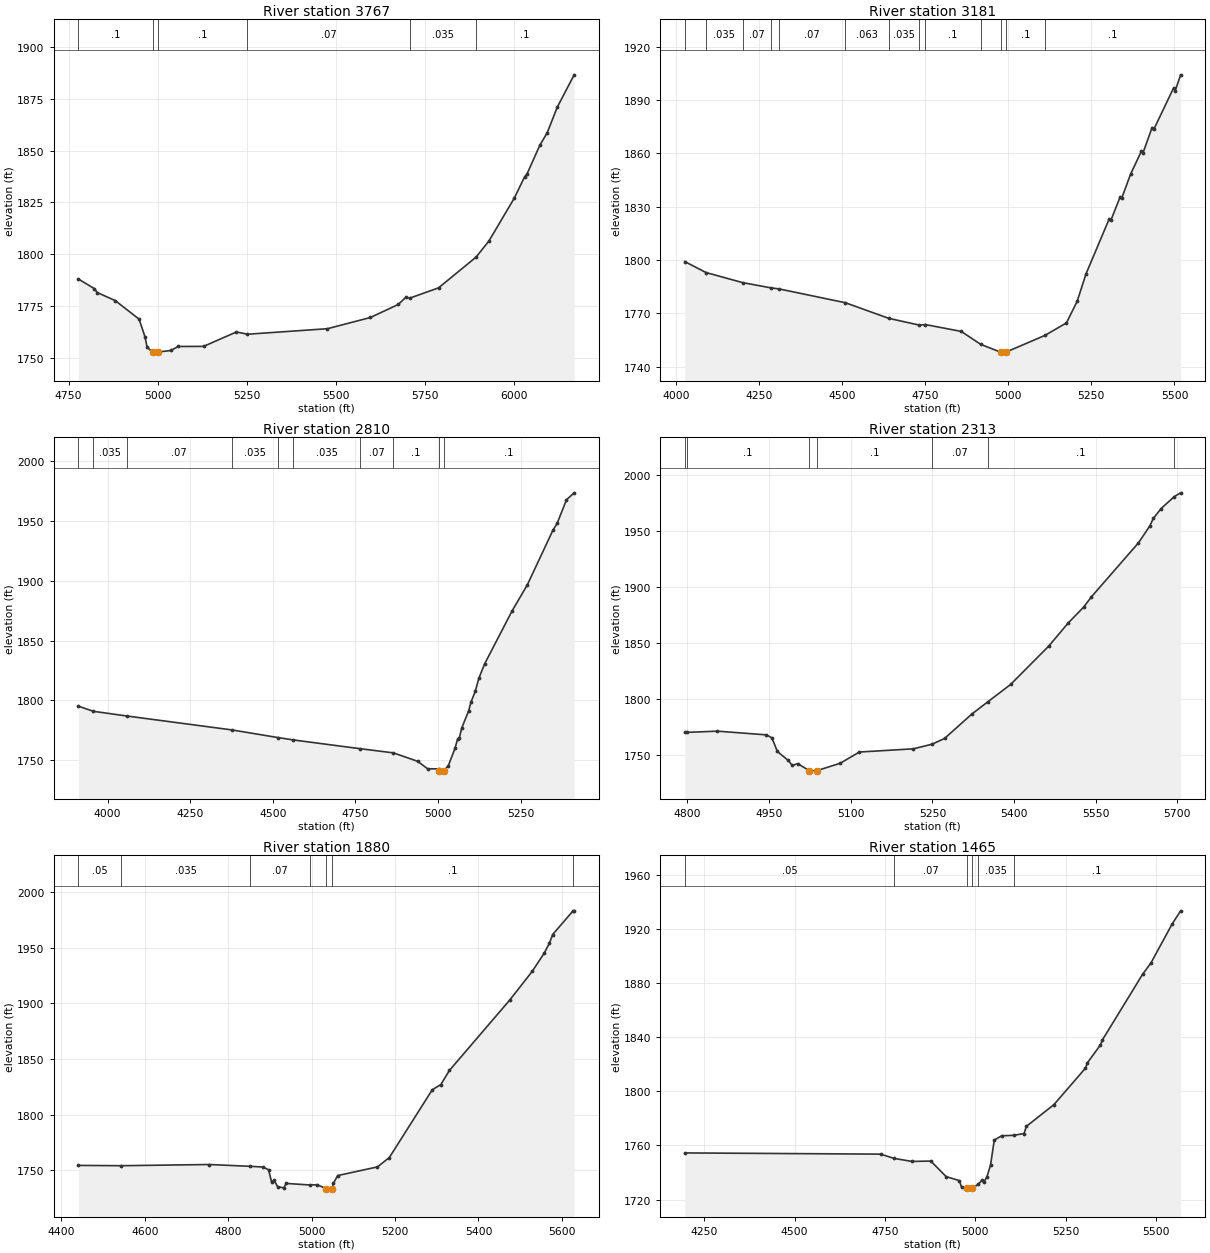
Type RM Length L Ch R = 1 ,3767    ,586,586,586
BEGIN DESCRIPTION:
Tegner Creek 7.0
END DESCRIPTION:
XS GIS Cut Line= 3
      1864924.99     13934175.01        1865125.       13934075.
      1866006.62     13933309.96
#Sta/Elev= 30
  4777.3 1788.02    4822 1783.41  4830.4 1781.48  4880.7 1777.61  4947.8 1768.64
  4964.6 1759.94  4970.2 1755.06  4985.4 1752.74  4985.9 1752.24  4999.7 1752.74
  5036.5 1753.51  5057.4 1755.44  5128.7  1755.5  5220.8 1762.45  5251.8 1761.36
  5476.2 1764.03  5596.7 1769.44  5674.7 1775.72  5695.6 1779.12    5708 1778.85
  5787.7 1783.74  5892.9 1798.55  5929.2 1806.39  6000.4 1827.08  6028.9 1837.25
  6035.5 1838.54  6071.7 1852.51  6092.5 1858.57    6121 1871.01  6168.2 1886.56
#Mann= 6 ,-1 , 0
  4777.3      .1       0  4985.4     .05       0  4999.7      .1       0
  5251.8     .07       0    5708    .035       0  5892.9      .1       0
Bank Sta=4985.4,4999.7
XS Rating Curve= 0 ,0
Exp/Cntr=0.3,0.1

Type RM Length L Ch R = 1 ,3181    ,371,371,371
BEGIN DESCRIPTION:
Tegner Creek 6.0
END DESCRIPTION:
XS GIS Cut Line= 3
      1864795.18     13934484.06      1865683.72     13934081.61
      1866175.03     13933924.99
#Sta/Elev= 30
  4027.4 1799.11  4091.3 1792.95  4201.2 1787.29  4287.8 1784.29    4311 1783.74
  4510.4 1775.97  4640.5 1767.22    4733 1763.38  4750.4 1763.72  4858.7 1759.85
  4917.4 1752.56  4977.9 1748.14  4978.4 1747.64  4992.3 1748.14  5110.5 1757.61
  5175.1 1764.63  5207.3 1776.75  5234.2  1792.3  5303.9 1823.19  5309.1 1822.47
  5336.1  1835.2  5341.3 1834.74  5368.3 1848.39  5400.5 1861.15  5405.7 1860.38
  5432.7 1874.43    5438  1873.5  5497.1 1896.62  5502.4 1895.24  5518.5  1904.1
#Mann= 13 ,-1 , 0
  4027.4      .1       0  4091.3    .035       0  4201.2     .07       0
  4287.8    .035       0    4311     .07       0  4510.4    .063       0
  4640.5    .035       0    4733    .063       0  4750.4      .1       0
  4917.4      .1       0  4977.9     .05       0  4992.3      .1       0
  5110.5      .1       0
Bank Sta=4977.9,4992.3
XS Rating Curve= 0 ,0
Exp/Cntr=0.3,0.1

Type RM Length L Ch R = 1 ,2810    ,497,497,497
BEGIN DESCRIPTION:
Tegner Creek 5.0
END DESCRIPTION:
XS GIS Cut Line= 3
      1864805.56     13934577.31        1865875.       13934375.
      1866274.99       13934275.
#Sta/Elev= 30
  3911.5 1795.28  3956.6 1790.99  4057.5 1787.08  4376.1 1775.45  4514.9 1769.12
  4562.3 1767.09  4764.2  1759.8  4865.2 1756.32  4938.8 1749.24  4968.6 1743.06
  5002.5 1742.97    5003 1741.59  5003.5 1741.09  5017.5 1741.59  5030.8 1745.26
  5051.4    1760  5059.2 1767.57  5064.3 1768.34  5072.1 1777.13  5092.7 1791.27
  5100.4 1798.96  5113.3 1807.97  5123.6 1818.41  5141.6 1830.73  5224.1 1874.57
  5270.5 1896.41  5347.8 1941.88  5360.7 1947.64    5389 1967.36  5412.2 1973.13
#Mann= 10 ,-1 , 0
  3911.5      .1       0  3956.6    .035       0  4057.5     .07       0
  4376.1    .035       0  4514.9     .07       0  4562.3    .035       0
  4764.2     .07       0  4865.2      .1       0    5003     .05       0
  5017.5      .1       0
Bank Sta=5003,5017.5
XS Rating Curve= 0 ,0
Exp/Cntr=0.3,0.1

Type RM Length L Ch R = 1 ,2313    ,433,433,433
BEGIN DESCRIPTION:
Tegner Creek 4.0
END DESCRIPTION:
XS GIS Cut Line= 3
      1865675.04       13934875.        1865875.       13934875.
        1866325.       13934325.
#Sta/Elev= 30
  4795.3 1770.46  4798.5 1770.49  4855.3 1771.58  4945.3 1768.27  4955.3 1765.58
  4965.3 1753.46  4985.3 1745.42  4992.8 1740.92  5002.4 1742.59  5023.9 1736.38
  5024.4 1735.88  5038.4 1736.38  5080.7 1742.92  5115.9 1752.94  5214.9 1755.79
  5249.6 1759.95  5272.3 1765.05  5321.9 1786.63  5351.4 1797.65  5393.6 1813.26
    5464 1847.71  5499.2 1868.07  5527.9 1882.44  5542.2 1891.63  5628.4 1939.73
  5649.2 1954.74  5655.7 1961.56    5670  1970.4  5694.2 1981.06  5705.9 1984.45
#Mann= 7 ,-1 , 0
  4795.3     .07       0  4798.5      .1       0  5023.9     .05       0
  5038.4      .1       0  5249.6     .07       0  5351.4      .1       0
  5694.2    .035       0
Bank Sta=5023.9,5038.4
XS Rating Curve= 0 ,0
Exp/Cntr=0.3,0.1

Type RM Length L Ch R = 1 ,1880    ,415,415,415
BEGIN DESCRIPTION:
Tegner Creek 3.0
END DESCRIPTION:
XS GIS Cut Line= 3
      1865875.02     13935424.97        1866225.       13934975.
        1866375.     13934375.02
#Sta/Elev= 30
  4440.8 1754.46  4543.6 1754.19  4754.8 1755.26  4852.1 1753.65  4883.3 1753.01
  4896.8 1750.52  4904.1 1739.42  4910.4 1740.99  4918.6 1735.25    4933 1734.32
  4939.4 1738.28  4997.2 1736.84  5013.4 1737.13  5034.5 1733.66    5035 1733.16
    5049 1733.66  5052.1 1738.33  5062.4 1745.33  5157.7  1753.1  5186.1 1761.43
  5289.2 1822.39  5309.8 1827.05  5330.4 1839.79  5474.7 1902.84  5528.8 1928.68
  5557.2 1944.87    5570 1953.93  5577.8 1961.75  5626.7 1983.02  5629.3 1983.02
#Mann= 7 ,-1 , 0
  4440.8     .05       0  4543.6    .035       0  4852.1     .07       0
  4997.2      .1       0  5034.5     .05       0    5049      .1       0
  5626.7    .035       0
Bank Sta=5034.5,5049
XS Rating Curve= 0 ,0
Exp/Cntr=0.3,0.1

Type RM Length L Ch R = 1 ,1465    ,394,394,394
BEGIN DESCRIPTION:
Tegner Creek 2.0
END DESCRIPTION:
XS GIS Cut Line= 3
       1865934.7     13935451.39      1866615.68      13935028.3
        1866475.     13934475.01
#Sta/Elev= 30
  4196.1 1754.45    4738 1753.55  4775.8 1750.38  4825.2 1748.15  4877.1 1748.43
  4919.6 1736.96  4956.2 1733.97  4962.1 1729.26    4978 1728.19  4978.5 1727.69
  4992.5 1728.19  5008.9 1731.41  5018.8 1734.27  5023.9 1733.01  5032.2 1736.54
  5042.5 1745.44  5052.8 1763.94  5073.4 1767.13  5106.5 1767.44  5135.3 1768.78
  5141.5 1774.04  5217.9 1790.13  5305.3 1817.12  5310.8 1821.13  5346.2 1834.04
    5352 1837.89  5463.8 1886.62  5486.2  1894.7  5545.7 1923.85  5568.7 1933.36
#Mann= 6 ,-1 , 0
  4196.1     .05       0  4775.8     .07       0    4978     .05       0
  4992.5     .07       0  5008.9    .035       0  5106.5      .1       0
Bank Sta=4978,4992.5
XS Rating Curve= 0 ,0
Exp/Cntr=0.3,0.1

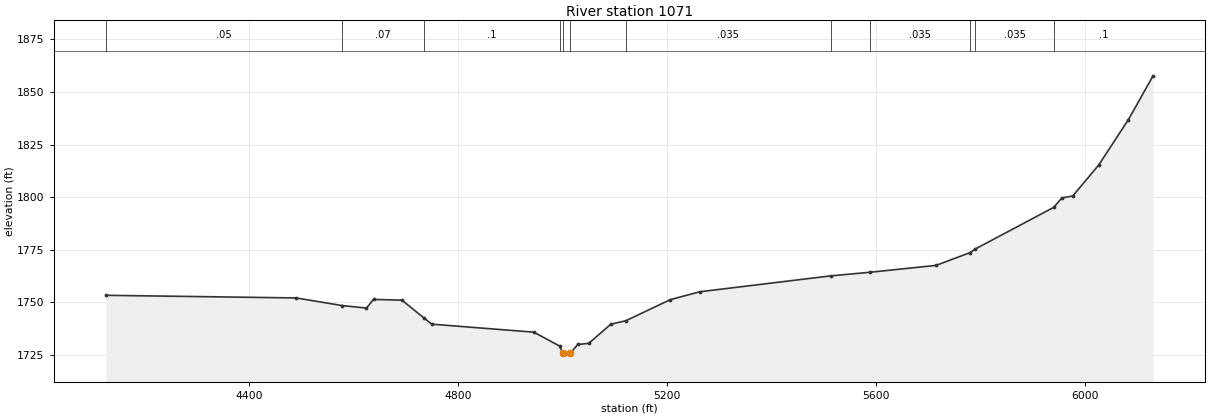
Type RM Length L Ch R = 1 ,1071    ,0,0,0
BEGIN DESCRIPTION:
Tegner Creek 1.0
END DESCRIPTION:
XS GIS Cut Line= 3
      1866040.55     13935602.79      1866861.28     13935320.85
      1867650.44     13934503.44
#Sta/Elev= 30
  4125.9  1753.4  4490.1 1752.14  4577.9 1748.53  4624.6 1747.34  4638.1 1751.45
  4692.4  1751.1  4734.5 1742.65  4749.6 1739.69  4944.8 1735.89  4994.1 1729.31
  5000.1 1725.96  5000.6 1725.46    5015 1725.96  5028.9 1730.04    5050 1730.59
  5092.4 1739.69    5121 1741.32  5205.6  1751.3  5262.2 1755.07  5513.1 1762.63
  5587.6 1764.33  5714.7 1767.61  5779.6 1773.66  5789.7  1775.4    5940  1795.2
  5955.2 1799.62  5976.3 1800.59    6026 1815.32  6082.6 1836.79  6129.9 1857.64
#Mann= 12 ,-1 , 0
  4125.9     .05       0  4577.9     .07       0  4734.5      .1       0
  4994.1     .07       0  5000.1     .05       0    5015     .07       0
    5121    .035       0  5513.1      .1       0  5587.6    .035       0
  5779.6      .1       0  5789.7    .035       0    5940      .1       0
Bank Sta=5000.1,5015
XS Rating Curve= 0 ,0
Exp/Cntr=0.3,0.1

Chan Stop Cuts=-1
Use User Specified Reach Order=0
Composite Channel Slope=5