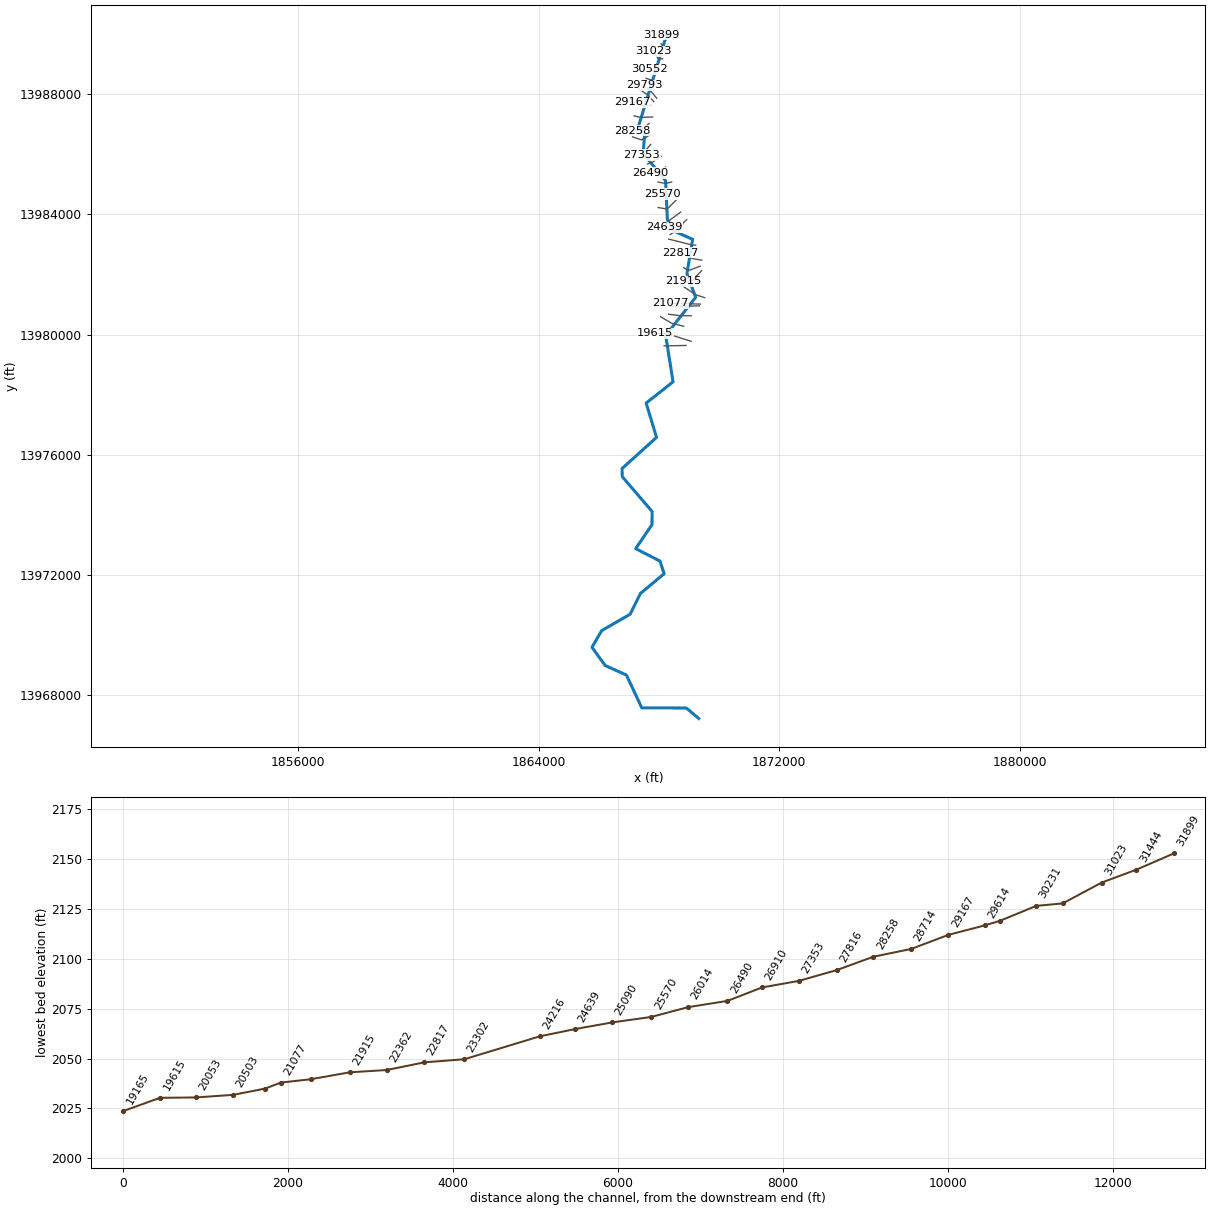
--- West Dry Branch.prj (project) ---

Proj Title=West Dry Branch Base Level Engineering
Current Plan=p01
Default Exp/Contr=0.3,0.1
English Units
Geom File=g01
Flow File=f01
Plan File=p01
BEGIN DESCRIPTION:
West Dry Branch
END DESCRIPTION:

--- West Dry Branch.p01 (plan) ---

Plan Title=Multiple Run
Short Identifier=Multiple
Geom File=g01
Flow File=f01
Subcritical Flow
K Sum by GR= 0
Std Step Tol= 0.01
Critical Tol= 0.01
Num of Std Step Trials= 20
Max Error Tol= 0.3
Flow Tol Ratio= 0.001
Split Flow NTrial= 30
Split Flow Tol= 0.02
Split Flow Ratio= 0.02
Log Output Level= 0
Friction Slope Method= 1
Unsteady Friction Slope Method= 2
Unsteady Bridges Friction Slope Method= 1
Parabolic Critical Depth
Global Vel Dist=  1 , 1 , 1
Global Log Level= 0
CheckData=True
Encroach Param= -1, 0, 0, 0
BEGIN DESCRIPTION:
Multiple Run
END DESCRIPTION:

--- West Dry Branch.f01 (steady flow) ---

Flow Title=Multiple
Number of Profiles=7
Profile Names=10-year,25-year,50-year,1pct_min,100-year,1pct_plu,500-year
River Rch & RM= West Dry Branch,Reach-1,31899
     539     880    1190     780    1557    3107    2628
River Rch & RM= West Dry Branch,Reach-1,30231
    1265    2159    3010    2025    4040    8061    7195
River Rch & RM= West Dry Branch,Reach-1,22817
    2574    4552    6494    4460    8899   17755   16530
River Rch & RM= West Dry Branch,Reach-1,16504
    3009    5354    7671    5288   10551   21052   19749
River Rch & RM= West Dry Branch,Reach-1,6341
    3313    5920    8503    5875   11722   23389   22041
Boundary for River Rch & Prof#=West Dry Branch,Reach-1,1
Up Type=0
Dn Type=3
Dn Slope=0.005
Boundary for River Rch & Prof#=West Dry Branch,Reach-1,2
Up Type=0
Dn Type=3
Dn Slope=0.005
Boundary for River Rch & Prof#=West Dry Branch,Reach-1,3
Up Type=0
Dn Type=3
Dn Slope=0.005
Boundary for River Rch & Prof#=West Dry Branch,Reach-1,4
Up Type=0
Dn Type=3
Dn Slope=0.005
Boundary for River Rch & Prof#=West Dry Branch,Reach-1,5
Up Type=0
Dn Type=3
Dn Slope=0.005
Boundary for River Rch & Prof#=West Dry Branch,Reach-1,6
Up Type=0
Dn Type=3
Dn Slope=0.005
Boundary for River Rch & Prof#=West Dry Branch,Reach-1,7
Up Type=0
Dn Type=3
Dn Slope=0.005

--- West Dry Branch.g01 (geometry) ---

Geom Title=Existing Conditions

River Reach=West Dry Branch,Reach-1
Reach XY= 30
      1868275.00     13990025.00      1867325.38     13986940.16
      1867523.96     13986664.35      1867478.76     13986026.56
      1868222.73     13985119.06      1868284.41     13983818.38
      1868515.29     13983435.75      1869122.94     13983169.15
      1868932.56     13982025.00      1869224.62     13981240.16
      1868227.06     13979969.14      1868471.39     13978426.50
      1867577.14     13977719.03      1867921.25     13976576.55
      1866774.51     13975540.20      1866782.81     13975268.81
      1867773.78     13974114.50      1867771.55     13973676.25
      1867228.45     13972876.49      1868038.35     13972461.64
      1868174.63     13972040.27      1867388.62     13971388.24
      1867041.68     13970691.64      1866097.72     13970149.14
      1865774.70     13969595.18      1866211.47     13968988.55
      1866919.92     13968669.96      1867433.30     13967578.06
      1868914.52     13967573.81      1869325.00     13967225.00

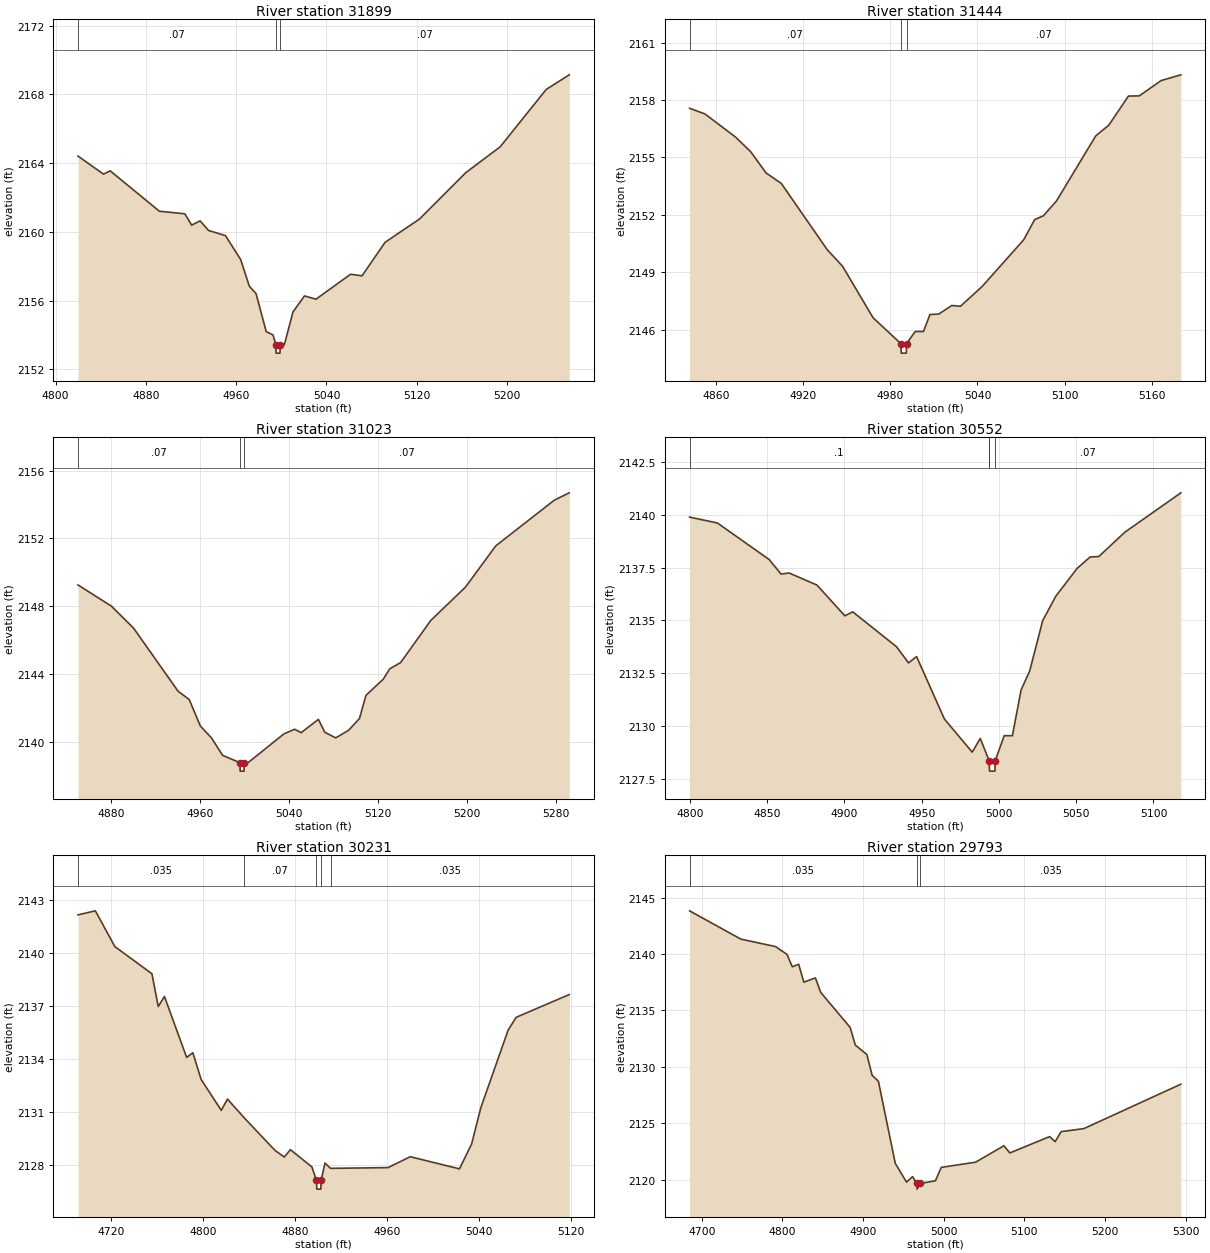
Type RM Length L Ch R = 1,31899,455,455,455
BEGIN DESCRIPTION:
West Dry Branch 69.0
END DESCRIPTION:
XS GIS Cut Line= 3
      1868475.02     13990025.01      1868325.00     13989925.00
      1868074.96     13989975.01
#Sta/Elev= 30
  4819.8 2164.41  4842.4 2163.36  4848.4 2163.55  4891.9 2161.20  4914.5 2161.05
  4920.5 2160.39  4928.0 2160.64  4935.5 2160.08  4950.5 2159.78  4964.0 2158.38
  4971.6 2156.84  4977.6 2156.40  4986.6 2154.19  4992.6 2154.00  4995.1 2153.44
  4995.3 2152.94  4998.8 2152.94  4999.1 2153.44  5002.7 2153.44  5010.3 2155.34
  5020.5 2156.27  5030.7 2156.08  5061.3 2157.53  5071.5 2157.44  5091.9 2159.39
  5122.5 2160.75  5163.3 2163.44  5193.9 2164.95  5234.7 2168.29  5255.1 2169.14
#Mann=3,-1,0
  4819.8    0.07       0  4995.1    0.05       0  4999.1    0.07       0
Bank Sta=4995.1,4999.1
Exp/Cntr=0.3,0.1

Type RM Length L Ch R = 1,31444,421,421,421
BEGIN DESCRIPTION:
West Dry Branch 68.0
END DESCRIPTION:
XS GIS Cut Line= 3
      1868324.96     13989475.01      1868175.00     13989525.00
      1868074.97     13989675.04
#Sta/Elev= 30
  4841.7 2157.57  4852.2 2157.28  4873.3 2156.07  4883.8 2155.30  4894.4 2154.19
  4904.9 2153.64  4936.5 2150.18  4947.1 2149.31  4968.1 2146.62  4987.2 2145.27
  4987.5 2144.77  4991.0 2144.77  4991.2 2145.27  4997.1 2145.90  5002.8 2145.90
  5007.3 2146.79  5013.3 2146.81  5022.3 2147.26  5028.3 2147.22  5043.3 2148.26
  5071.9 2150.70  5079.4 2151.75  5085.4 2151.95  5094.4 2152.72  5121.5 2156.13
  5130.5 2156.69  5144.0 2158.21  5151.5 2158.22  5166.5 2159.02  5180.1 2159.32
#Mann=3,-1,0
  4841.7    0.07       0  4987.2    0.05       0  4991.2    0.07       0
Bank Sta=4987.2,4991.2
Exp/Cntr=0.3,0.1

Type RM Length L Ch R = 1,31023,471,471,471
BEGIN DESCRIPTION:
West Dry Branch 67.0
END DESCRIPTION:
XS GIS Cut Line= 3
      1868125.02     13989175.00      1867975.00     13989175.00
      1867824.98     13989425.03
#Sta/Elev= 30
  4850.0 2149.26  4880.0 2148.01  4900.0 2146.71  4940.0 2142.99  4950.0 2142.50
  4960.0 2140.94  4970.0 2140.24  4980.0 2139.21  4995.5 2138.78  4995.8 2138.28
  4999.3 2138.28  4999.5 2138.78  5002.9 2138.78  5035.0 2140.47  5044.7 2140.75
  5050.6 2140.55  5066.1 2141.33  5071.9 2140.57  5081.7 2140.24  5093.3 2140.69
  5103.0 2141.38  5108.9 2142.75  5124.4 2143.70  5130.2 2144.31  5140.0 2144.68
  5167.2 2147.17  5198.3 2149.13  5225.5 2151.56  5278.0 2154.25  5291.6 2154.69
#Mann=3,-1,0
  4850.0    0.07       0  4995.5    0.05       0  4999.5    0.07       0
Bank Sta=4995.5,4999.5
Exp/Cntr=0.3,0.1

Type RM Length L Ch R = 1,30552,321,321,321
BEGIN DESCRIPTION:
West Dry Branch 66.0
END DESCRIPTION:
XS GIS Cut Line= 3
      1867974.97     13988824.99      1867775.00     13988775.00
      1867675.03     13988824.99
#Sta/Elev= 30
  4799.8 2139.90  4817.8 2139.62  4851.3 2137.89  4859.0 2137.20  4864.2 2137.25
  4882.2 2136.68  4900.3 2135.22  4905.4 2135.41  4933.8 2133.75  4941.5 2132.99
  4946.7 2133.29  4964.7 2130.33  4982.7 2128.76  4987.9 2129.41  4993.5 2128.38
  4993.6 2128.36  4993.9 2127.86  4997.4 2127.86  4997.6 2128.36  5003.4 2129.54
  5008.7 2129.54  5014.3 2131.70  5019.9 2132.61  5028.3 2134.99  5036.7 2136.14
  5050.6 2137.47  5059.0 2138.01  5064.6 2138.03  5081.4 2139.18  5117.7 2141.05
#Mann=4,-1,0
  4799.8     0.1       0  4993.5    0.07       0  4993.6    0.05       0
  4997.6    0.07       0
Bank Sta=4993.6,4997.6
Exp/Cntr=0.3,0.1

Type RM Length L Ch R = 1,30231,438,438,438
BEGIN DESCRIPTION:
West Dry Branch 65.0
END DESCRIPTION:
XS GIS Cut Line= 3
      1867975.02     13988374.99      1867693.51     13988482.58
      1867575.04     13988524.99
#Sta/Elev= 30
  4691.2 2142.17  4706.3 2142.40  4723.3 2140.37  4755.5 2138.83  4761.0 2136.97
  4766.4 2137.54  4785.7 2134.08  4791.1 2134.35  4798.3 2132.83  4815.8 2131.08
  4821.2 2131.72  4835.4 2130.68  4862.5 2128.81  4870.6 2128.43  4875.9 2128.85
  4894.6 2127.87  4898.6 2127.11  4898.9 2126.61  4902.4 2126.61  4902.6 2127.11
  4906.0 2128.09  4910.8 2127.79  4960.8 2127.83  4980.1 2128.45  5022.9 2127.76
  5033.5 2129.17  5041.5 2131.23  5065.3 2135.64  5072.3 2136.36  5118.4 2137.65
#Mann=5,-1,0
  4691.2   0.035       0  4835.4    0.07       0  4898.6   0.035       0
  4902.6    0.07       0  4910.8   0.035       0
Bank Sta=4898.6,4902.6
Exp/Cntr=0.3,0.1

Type RM Length L Ch R = 1,29793,179,179,179
BEGIN DESCRIPTION:
West Dry Branch 4.1
END DESCRIPTION:
XS GIS Cut Line= 3
      1867930.16     13987860.55      1867757.43     13988069.49
      1867509.47     13988299.50
#Sta/Elev= 30
  4684.9 2143.84  4748.5 2141.33  4791.5 2140.67  4805.8 2139.97  4812.3 2138.88
  4820.2 2139.10  4826.6 2137.51  4841.0 2137.89  4847.5 2136.61  4884.0 2133.50
  4890.5 2131.93  4904.8 2131.09  4911.3 2129.25  4919.1 2128.72  4940.0 2121.44
  4954.0 2119.77  4961.4 2120.26  4966.8 2119.65  4967.0 2119.15  4970.8 2119.65
  4989.8 2119.89  4997.1 2121.08  5039.6 2121.54  5074.8 2123.00  5082.1 2122.36
  5131.5 2123.81  5138.3 2123.36  5145.7 2124.25  5174.0 2124.52  5294.2 2128.46
#Mann=3,-1,0
  4684.9   0.035       0  4966.8   0.035       0  4970.8   0.035       0
Bank Sta=4966.8,4970.8
Exp/Cntr=0.3,0.1

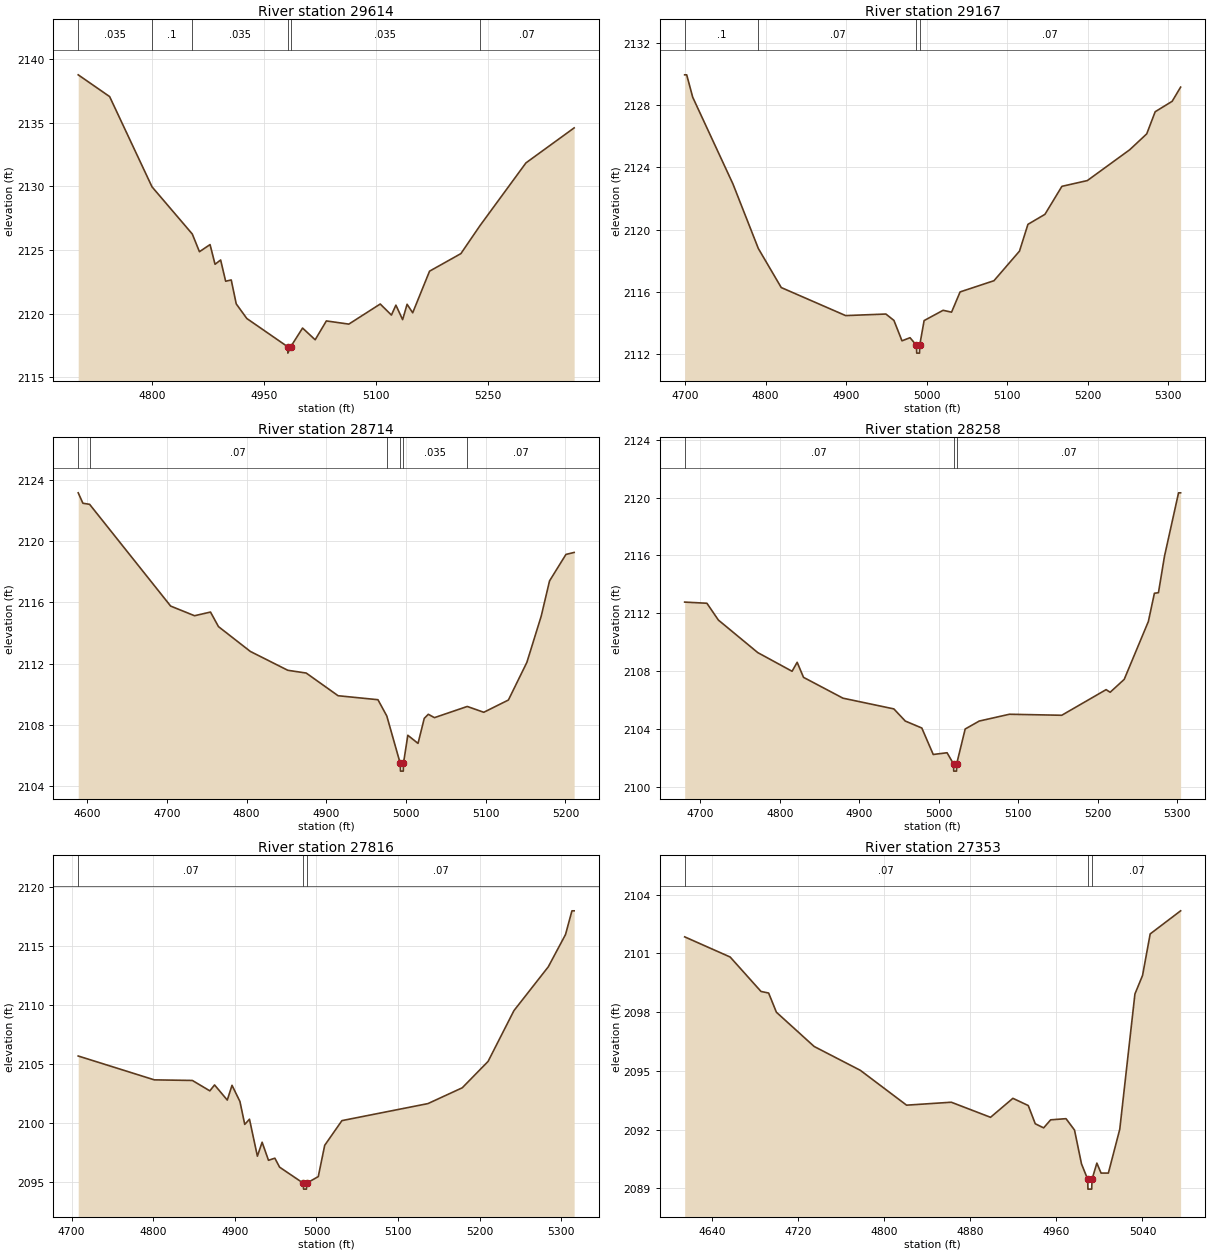
Type RM Length L Ch R = 1,29614,447,447,447
BEGIN DESCRIPTION:
West Dry Branch 64.0
END DESCRIPTION:
XS GIS Cut Line= 3
      1867828.45     13987748.99      1867625.00     13987975.00
      1867324.96     13988175.03
#Sta/Elev= 30
  4700.7 2138.76  4742.8 2137.05  4799.6 2129.96  4853.6 2126.25  4863.2 2124.86
  4877.4 2125.42  4884.1 2123.87  4891.6 2124.21  4898.3 2122.54  4905.8 2122.64
  4912.5 2120.76  4926.7 2119.61  4981.5 2117.39  4981.7 2116.89  4985.5 2117.39
  5001.4 2118.86  5018.3 2117.94  5033.3 2119.42  5063.4 2119.17  5105.5 2120.75
  5120.5 2119.88  5126.5 2120.66  5135.5 2119.52  5141.5 2120.73  5149.0 2120.06
  5171.6 2123.33  5213.6 2124.71  5239.1 2126.90  5300.8 2131.84  5365.4 2134.59
#Mann=6,-1,0
  4700.7   0.035       0  4799.6     0.1       0  4853.6   0.035       0
  4981.5   0.035       0  4985.5   0.035       0  5239.1    0.07       0
Bank Sta=4981.5,4985.5
Exp/Cntr=0.3,0.1

Type RM Length L Ch R = 1,29167,453,453,453
BEGIN DESCRIPTION:
West Dry Branch 63.0
END DESCRIPTION:
XS GIS Cut Line= 3
      1867725.01     13987625.00      1867425.00     13987625.00
      1867125.03     13987724.99
#Sta/Elev= 30
  4699.4 2129.94  4701.9 2129.94  4709.4 2128.50  4759.4 2122.93  4790.9 2118.79
  4819.4 2116.28  4899.4 2114.48  4949.4 2114.58  4959.4 2114.17  4969.4 2112.86
  4979.4 2113.06  4987.4 2112.57  4987.7 2112.07  4991.2 2112.07  4991.4 2112.57
  4996.9 2114.16  5020.5 2114.82  5031.0 2114.70  5041.6 2116.00  5083.7 2116.72
  5115.4 2118.62  5125.9 2120.34  5147.0 2120.98  5168.1 2122.78  5199.7 2123.15
  5252.4 2125.13  5273.5 2126.15  5284.0 2127.57  5305.1 2128.24  5315.6 2129.15
#Mann=4,-1,0
  4699.4     0.1       0  4790.9    0.07       0  4987.4    0.05       0
  4991.4    0.07       0
Bank Sta=4987.4,4991.4
Exp/Cntr=0.3,0.1

Type RM Length L Ch R = 1,28714,456,456,456
BEGIN DESCRIPTION:
West Dry Branch 62.0
END DESCRIPTION:
XS GIS Cut Line= 3
      1867790.89     13987238.77      1867375.00     13987225.00
      1867174.98     13987275.01
#Sta/Elev= 30
  4588.7 2123.14  4594.6 2122.46  4603.0 2122.39  4704.7 2115.75  4734.7 2115.12
  4754.7 2115.36  4764.7 2114.41  4804.7 2112.79  4851.7 2111.56  4874.8 2111.38
  4914.8 2109.90  4964.8 2109.64  4975.9 2108.58  4992.8 2105.48  4993.1 2104.98
  4996.6 2104.98  4996.8 2105.48  5002.3 2107.32  5015.1 2106.79  5022.9 2108.42
  5028.0 2108.69  5035.7 2108.47  5076.9 2109.20  5097.6 2108.82  5128.5 2109.62
  5151.7 2112.08  5169.7 2115.10  5180.1 2117.39  5200.7 2119.12  5211.0 2119.25
#Mann=6,-1,0
  4588.7   0.035       0  4603.0    0.07       0  4975.9   0.035       0
  4992.8   0.035       0  4996.8   0.035       0  5076.9    0.07       0
Bank Sta=4992.8,4996.8
Exp/Cntr=0.3,0.1

Type RM Length L Ch R = 1,28258,442,442,442
BEGIN DESCRIPTION:
West Dry Branch 61.0
END DESCRIPTION:
XS GIS Cut Line= 3
      1867674.98     13987024.98      1867425.00     13986825.00
      1867124.97     13986774.99
#Sta/Elev= 30
  4680.1 2112.78  4708.1 2112.70  4722.5 2111.54  4772.1 2109.29  4815.3 2108.00
  4821.7 2108.62  4829.7 2107.58  4879.4 2106.14  4943.4 2105.40  4957.8 2104.56
  4978.6 2104.08  4993.0 2102.25  5010.4 2102.37  5018.5 2101.60  5018.8 2101.10
  5022.3 2101.10  5022.5 2101.60  5033.2 2104.01  5050.9 2104.56  5088.9 2105.03
  5154.8 2104.96  5210.6 2106.73  5215.7 2106.55  5233.4 2107.44  5263.8 2111.44
  5271.4 2113.39  5276.5 2113.43  5284.1 2115.95  5301.8 2120.33  5304.4 2120.33
#Mann=3,-1,0
  4680.1    0.07       0  5018.5    0.05       0  5022.5    0.07       0
Bank Sta=5018.5,5022.5
Exp/Cntr=0.3,0.1

Type RM Length L Ch R = 1,27816,463,463,463
BEGIN DESCRIPTION:
West Dry Branch 60.0
END DESCRIPTION:
XS GIS Cut Line= 3
      1867674.98     13986624.99      1867425.00     13986475.00
      1867124.96     13986575.01
#Sta/Elev= 30
  4708.0 2105.69  4801.3 2103.67  4847.9 2103.62  4869.3 2102.74  4875.1 2103.24
  4890.7 2101.96  4896.5 2103.21  4906.2 2101.84  4912.1 2099.90  4917.9 2100.34
  4927.6 2097.21  4933.4 2098.39  4941.2 2096.86  4949.0 2097.04  4954.8 2096.28
  4983.9 2094.92  4984.2 2094.42  4987.7 2094.42  4987.9 2094.92  5002.2 2095.48
  5010.1 2098.13  5031.2 2100.22  5136.6 2101.66  5178.7 2103.00  5210.3 2105.23
  5242.0 2109.53  5284.1 2113.24  5305.2 2115.97  5313.1 2117.98  5315.8 2117.98
#Mann=3,-1,0
  4708.0    0.07       0  4983.9    0.05       0  4987.9    0.07       0
Bank Sta=4983.9,4987.9
Exp/Cntr=0.3,0.1

Type RM Length L Ch R = 1,27353,443,443,443
BEGIN DESCRIPTION:
West Dry Branch 59.0
END DESCRIPTION:
XS GIS Cut Line= 3
      1867725.02     13986325.02      1867475.00     13986025.00
      1867424.97     13985974.97
#Sta/Elev= 30
  4614.2 2101.85  4656.5 2100.82  4685.2 2099.06  4692.3 2098.98  4699.5 2098.00
  4734.6 2096.25  4777.6 2095.03  4820.6 2093.25  4862.2 2093.40  4898.7 2092.63
  4919.5 2093.60  4933.8 2093.23  4940.3 2092.30  4948.1 2092.09  4954.6 2092.50
  4968.9 2092.56  4976.8 2091.98  4983.3 2090.25  4989.1 2089.46  4989.3 2088.96
  4992.8 2088.96  4993.1 2089.46  4997.6 2090.29  5001.5 2089.78  5008.3 2089.78
  5018.9 2092.02  5033.0 2098.93  5040.1 2099.88  5047.2 2102.00  5075.5 2103.18
#Mann=3,-1,0
  4614.2    0.07       0  4989.1    0.05       0  4993.1    0.07       0
Bank Sta=4989.1,4993.1
Exp/Cntr=0.3,0.1

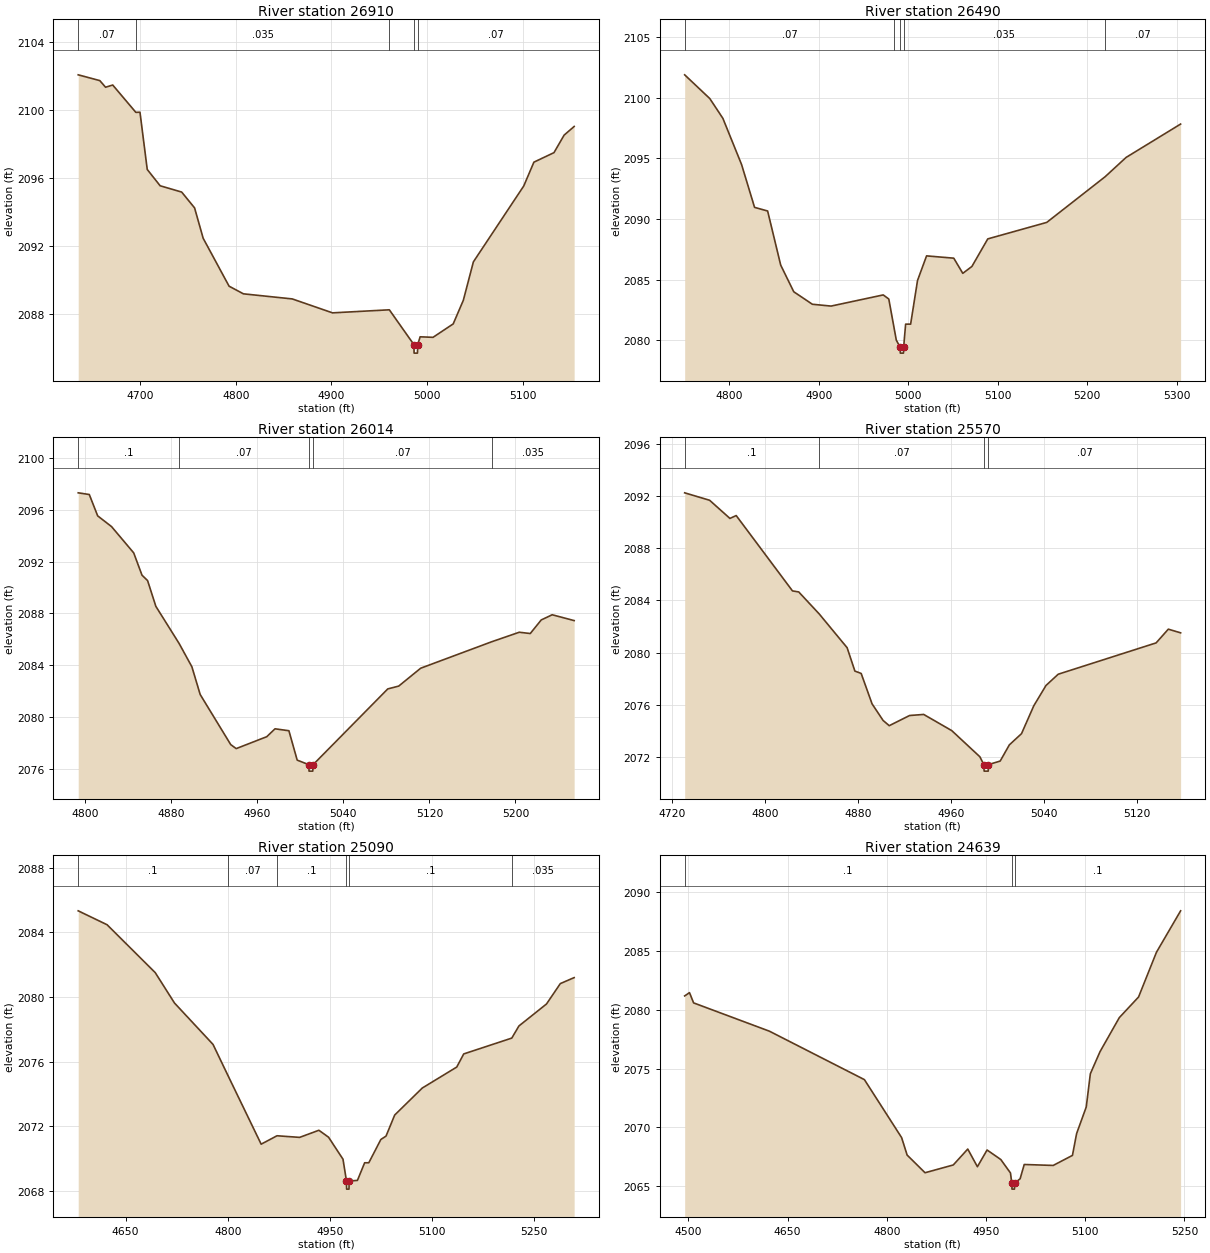
Type RM Length L Ch R = 1,26910,420,420,420
BEGIN DESCRIPTION:
West Dry Branch 58.0
END DESCRIPTION:
XS GIS Cut Line= 3
      1868075.04     13985925.03      1867775.00     13985725.00
      1867625.01     13985675.00
#Sta/Elev= 30
  4635.1 2102.08  4657.7 2101.74  4663.7 2101.35  4671.2 2101.48  4695.4 2099.87
  4699.7 2099.88  4707.3 2096.51  4720.8 2095.55  4743.3 2095.18  4756.8 2094.25
  4765.8 2092.46  4792.9 2089.64  4807.9 2089.19  4859.0 2088.89  4901.1 2088.07
  4960.5 2088.25  4986.2 2086.20  4986.4 2085.70  4989.9 2085.70  4990.2 2086.20
  4992.7 2086.66  5006.2 2086.63  5027.3 2087.42  5037.9 2088.81  5048.4 2091.07
  5101.1 2095.54  5111.7 2096.94  5132.7 2097.50  5143.3 2098.53  5153.8 2099.04
#Mann=5,-1,0
  4635.1    0.07       0  4695.4   0.035       0  4960.5    0.07       0
  4986.2    0.05       0  4990.2    0.07       0
Bank Sta=4986.2,4990.2
Exp/Cntr=0.3,0.1

Type RM Length L Ch R = 1,26490,476,476,476
BEGIN DESCRIPTION:
West Dry Branch 57.0
END DESCRIPTION:
XS GIS Cut Line= 3
      1868225.01     13985575.01      1868025.00     13985425.00
      1867724.95     13985374.99
#Sta/Elev= 30
  4750.2 2101.89  4778.3 2099.93  4792.9 2098.30  4813.8 2094.49  4828.3 2090.96
  4842.9 2090.66  4857.5 2086.20  4872.1 2084.00  4892.9 2082.97  4913.8 2082.82
  4972.1 2083.74  4978.3 2083.40  4984.2 2081.02  4986.7 2080.01  4990.9 2079.44
  4991.2 2078.94  4994.7 2078.94  4994.9 2079.44  4997.1 2081.33  5002.7 2081.33
  5010.4 2084.93  5020.5 2086.96  5050.9 2086.77  5061.0 2085.52  5071.2 2086.09
  5088.9 2088.36  5154.8 2089.72  5220.1 2093.49  5243.5 2095.08  5304.4 2097.83
#Mann=5,-1,0
  4750.2    0.07       0  4984.2   0.035       0  4990.9   0.035       0
  4994.9   0.035       0  5220.1    0.07       0
Bank Sta=4990.9,4994.9
Exp/Cntr=0.3,0.1

Type RM Length L Ch R = 1,26014,444,444,444
BEGIN DESCRIPTION:
West Dry Branch 56.0
END DESCRIPTION:
XS GIS Cut Line= 3
      1868425.03     13985075.01      1868225.00     13985025.00
      1867975.03     13985074.99
#Sta/Elev= 30
  4793.5 2097.32  4803.8 2097.19  4811.6 2095.54  4824.5 2094.71  4845.1 2092.68
  4852.8 2090.96  4858.0 2090.54  4865.7 2088.55  4887.4 2085.67  4899.2 2083.88
  4906.9 2081.74  4935.3 2077.87  4940.4 2077.56  4968.8 2078.48  4976.5 2079.09
  4989.4 2078.94  4997.1 2076.67  5007.9 2076.32  5008.1 2075.82  5011.6 2075.82
  5011.9 2076.32  5081.3 2082.17  5091.5 2082.39  5111.9 2083.77  5177.8 2085.81
  5203.6 2086.55  5213.8 2086.45  5224.0 2087.50  5234.2 2087.90  5254.6 2087.45
#Mann=5,-1,0
  4793.5     0.1       0  4887.4    0.07       0  5007.9    0.05       0
  5011.9    0.07       0  5177.8   0.035       0
Bank Sta=5007.9,5011.9
Exp/Cntr=0.3,0.1

Type RM Length L Ch R = 1,25570,480,480,480
BEGIN DESCRIPTION:
West Dry Branch 55.0
END DESCRIPTION:
XS GIS Cut Line= 3
      1868524.99     13984724.99      1868275.00     13984625.00
      1868124.96     13984675.01
#Sta/Elev= 30
  4730.6 2092.23  4752.1 2091.66  4769.6 2090.27  4775.0 2090.49  4823.5 2084.72
  4828.9 2084.64  4846.6 2082.95  4870.6 2080.37  4877.3 2078.58  4882.7 2078.40
  4892.1 2076.07  4901.6 2074.80  4906.9 2074.40  4924.5 2075.18  4936.6 2075.26
  4960.8 2074.02  4985.0 2072.02  4988.4 2071.42  4988.7 2070.92  4992.2 2070.92
  4992.4 2071.42  5002.5 2071.69  5010.4 2072.93  5020.9 2073.79  5031.5 2075.93
  5042.0 2077.48  5052.5 2078.34  5136.9 2080.74  5147.4 2081.79  5158.0 2081.51
#Mann=4,-1,0
  4730.6     0.1       0  4846.6    0.07       0  4988.4    0.05       0
  4992.4    0.07       0
Bank Sta=4988.4,4992.4
Exp/Cntr=0.3,0.1

Type RM Length L Ch R = 1,25090,451,451,451
BEGIN DESCRIPTION:
West Dry Branch 54.0
END DESCRIPTION:
XS GIS Cut Line= 3
      1868574.98     13984474.98      1868275.00     13984175.00
      1867974.98     13984225.00
#Sta/Elev= 30
  4580.3 2085.33  4622.7 2084.47  4693.4 2081.51  4721.7 2079.63  4778.3 2077.07
  4800.3 2075.14  4849.0 2070.90  4872.3 2071.42  4905.5 2071.32  4933.8 2071.76
  4948.0 2071.33  4969.2 2069.97  4974.3 2068.62  4974.5 2068.12  4978.0 2068.12
  4978.3 2068.62  4990.4 2068.66  5001.0 2069.75  5007.1 2069.75  5024.8 2071.19
  5032.4 2071.40  5045.1 2072.70  5085.6 2074.37  5136.3 2075.67  5146.5 2076.48
  5217.1 2077.46  5227.6 2078.21  5268.1 2079.57  5288.4 2080.83  5308.7 2081.20
#Mann=6,-1,0
  4580.3     0.1       0  4800.3    0.07       0  4872.3     0.1       0
  4974.3    0.05       0  4978.3     0.1       0  5217.1   0.035       0
Bank Sta=4974.3,4978.3
Exp/Cntr=0.3,0.1

Type RM Length L Ch R = 1,24639,423,423,423
BEGIN DESCRIPTION:
West Dry Branch 53.0
END DESCRIPTION:
XS GIS Cut Line= 3
      1868724.97     13984074.98      1868325.00     13983775.00
      1868174.98     13983574.97
#Sta/Elev= 30
  4494.3 2081.16  4501.6 2081.44  4507.8 2080.57  4622.4 2078.17  4766.1 2074.06
  4822.4 2069.14  4830.7 2067.66  4857.8 2066.16  4900.5 2066.82  4922.4 2068.17
  4937.0 2066.67  4951.6 2068.09  4972.4 2067.28  4987.0 2066.14  4989.0 2065.27
  4989.3 2064.77  4993.0 2064.77  4993.2 2065.27  5001.6 2065.65  5007.8 2066.86
  5051.6 2066.78  5080.7 2067.63  5087.0 2069.48  5101.6 2071.74  5107.8 2074.56
  5122.4 2076.43  5151.6 2079.32  5180.7 2081.07  5207.8 2084.87  5244.3 2088.38
#Mann=3,-1,0
  4494.3     0.1       0  4989.0    0.05       0  4993.2     0.1       0
Bank Sta=4989,4993.2
Exp/Cntr=0.3,0.1

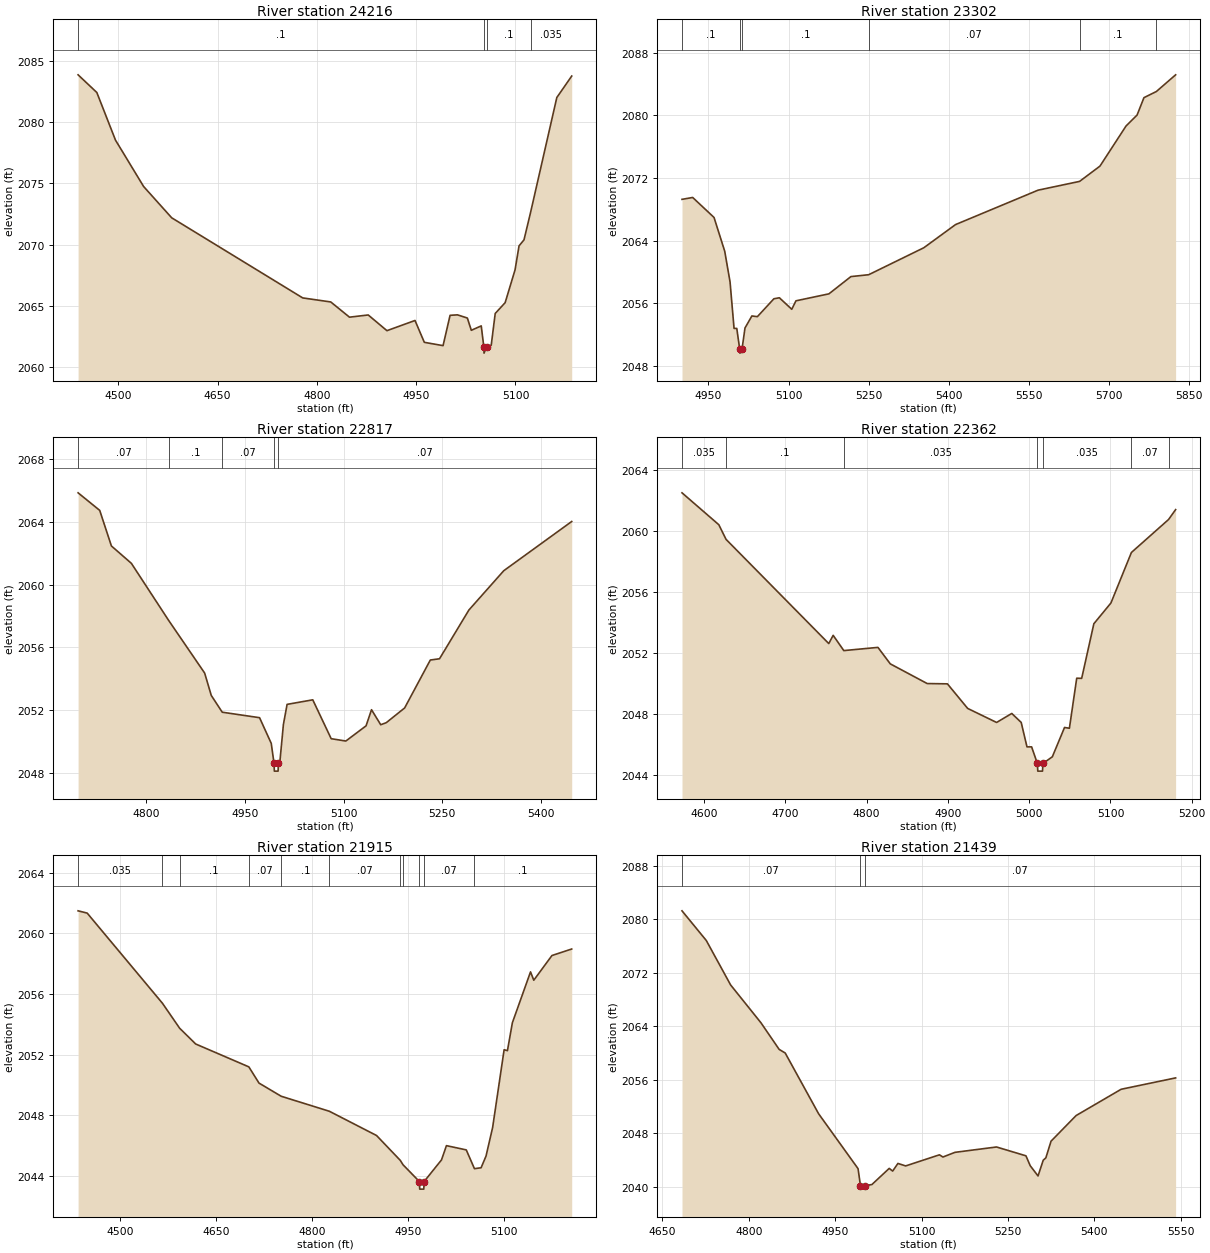
Type RM Length L Ch R = 1,24216,914,914,914
BEGIN DESCRIPTION:
West Dry Branch 52.0
END DESCRIPTION:
XS GIS Cut Line= 3
      1868924.98     13983824.98      1868525.00     13983425.00
      1868375.03     13983325.02
#Sta/Elev= 30
  4439.1 2083.84  4467.4 2082.40  4495.6 2078.52  4538.1 2074.74  4580.5 2072.19
  4778.5 2065.66  4820.9 2065.33  4849.2 2064.09  4877.5 2064.27  4905.8 2062.99
  4948.2 2063.82  4962.3 2062.04  4990.6 2061.77  5001.2 2064.24  5012.3 2064.28
  5027.3 2064.02  5033.3 2063.02  5048.3 2063.38  5052.2 2061.66  5052.5 2061.16
  5056.4 2061.66  5063.4 2061.81  5069.4 2064.39  5084.4 2065.27  5099.4 2067.95
  5105.4 2069.90  5112.9 2070.39  5122.9 2072.64  5162.5 2081.99  5185.0 2083.74
#Mann=4,-1,0
  4439.1     0.1       0  5052.2    0.05       0  5056.4     0.1       0
  5122.9   0.035       0
Bank Sta=5052.2,5056.4
Exp/Cntr=0.3,0.1

Type RM Length L Ch R = 1,23302,485,485,485
BEGIN DESCRIPTION:
West Dry Branch 51.0
END DESCRIPTION:
XS GIS Cut Line= 3
      1869224.98     13982975.00      1869125.00     13982975.00
      1868325.00     13983175.00
#Sta/Elev= 30
  4900.4 2069.28  4920.4 2069.52  4960.4 2066.97  4980.4 2062.67  4990.4 2058.75
  4997.9 2052.82  5003.0 2052.82  5008.5 2050.17  5008.8 2049.67  5012.8 2050.17
  5018.4 2052.88  5031.3 2054.41  5041.6 2054.32  5072.5 2056.60  5082.8 2056.73
  5106.0 2055.26  5113.8 2056.34  5175.6 2057.23  5216.8 2059.43  5250.1 2059.67
  5353.4 2063.11  5412.7 2066.06  5567.3 2070.45  5645.1 2071.57  5683.3 2073.52
  5732.2 2078.64  5752.8 2080.03  5765.7 2082.25  5788.9 2083.03  5825.0 2085.16
#Mann=6,-1,0
  4900.4     0.1       0  5008.5    0.05       0  5012.8     0.1       0
  5250.1    0.07       0  5645.1     0.1       0  5788.9    0.07       0
Bank Sta=5008.5,5012.8
Exp/Cntr=0.3,0.1

Type RM Length L Ch R = 1,22817,455,455,455
BEGIN DESCRIPTION:
West Dry Branch 50.0
END DESCRIPTION:
XS GIS Cut Line= 3
      1869424.96     13982475.01      1869125.00     13982525.00
      1868725.01     13982724.99
#Sta/Elev= 30
  4695.9 2065.87  4728.8 2064.75  4746.6 2062.48  4777.0 2061.37  4833.7 2057.73
  4888.5 2054.37  4898.6 2052.94  4915.3 2051.87  4972.1 2051.52  4989.9 2049.88
  4994.1 2048.61  4994.6 2048.11  5000.3 2048.11  5000.8 2048.61  5002.8 2048.61
  5008.4 2051.09  5014.0 2052.37  5053.1 2052.66  5081.1 2050.18  5103.4 2050.03
  5134.2 2051.00  5142.5 2052.03  5156.5 2051.07  5164.9 2051.20  5192.9 2052.14
  5232.0 2055.20  5246.0 2055.28  5290.7 2058.39  5343.8 2060.90  5447.2 2064.04
#Mann=5,-1,0
  4695.9    0.07       0  4833.7     0.1       0  4915.3    0.07       0
  4994.1    0.05       0  5000.8    0.07       0
Bank Sta=4994.1,5000.8
Exp/Cntr=0.3,0.1

Type RM Length L Ch R = 1,22362,447,447,447
BEGIN DESCRIPTION:
West Dry Branch 49.0
END DESCRIPTION:
XS GIS Cut Line= 3
      1869374.96     13982274.98      1868975.00     13982125.00
      1868825.03     13982224.98
#Sta/Elev= 30
  4572.8 2062.51  4618.1 2060.42  4627.0 2059.46  4753.4 2052.63  4758.8 2053.17
  4771.9 2052.17  4813.9 2052.38  4829.1 2051.30  4874.5 2050.01  4899.4 2049.99
  4924.3 2048.38  4959.9 2047.46  4978.6 2048.05  4990.2 2047.46  4997.3 2045.86
  5003.0 2045.86  5010.1 2044.77  5010.6 2044.27  5016.4 2044.27  5016.9 2044.77
  5028.5 2045.21  5043.5 2047.13  5049.5 2047.08  5058.5 2050.36  5064.6 2050.35
  5079.6 2053.93  5100.6 2055.29  5125.8 2058.60  5171.5 2060.76  5180.2 2061.41
#Mann=7,-1,0
  4572.8   0.035       0  4627.0     0.1       0  4771.9   0.035       0
  5010.1   0.035       0  5016.9   0.035       0  5125.8    0.07       0
  5171.5   0.035       0
Bank Sta=5010.1,5016.9
Exp/Cntr=0.3,0.1

Type RM Length L Ch R = 1,21915,476,476,476
BEGIN DESCRIPTION:
West Dry Branch 48.0
END DESCRIPTION:
XS GIS Cut Line= 3
      1869425.03     13982125.03      1869025.00     13981725.00
      1868824.99     13981775.00
#Sta/Elev= 30
  4433.8 2061.49  4448.0 2061.34  4565.7 2055.39  4592.6 2053.74  4617.7 2052.70
  4700.8 2051.19  4716.7 2050.12  4751.4 2049.25  4826.7 2048.26  4900.5 2046.66
  4937.6 2045.02  4941.9 2044.73  4967.5 2043.62  4968.0 2043.12  4974.4 2043.12
  4974.9 2043.62  5002.1 2045.05  5009.8 2045.99  5040.8 2045.71  5053.6 2044.47
  5064.0 2044.53  5071.7 2045.30  5082.0 2047.18  5100.0 2052.32  5105.2 2052.26
  5112.9 2054.10  5141.3 2057.46  5146.4 2056.91  5174.8 2058.54  5205.7 2058.97
#Mann=11,-1,0
  4433.8   0.035       0  4565.7    0.07       0  4592.6     0.1       0
  4700.8    0.07       0  4751.4     0.1       0  4826.7    0.07       0
  4937.6     0.1       0  4941.9    0.07       0  4967.5    0.05       0
  4974.9    0.07       0  5053.6     0.1       0
Bank Sta=4967.5,4974.9
Exp/Cntr=0.3,0.1

Type RM Length L Ch R = 1,21439,362,362,362
BEGIN DESCRIPTION:
West Dry Branch 47.0
END DESCRIPTION:
XS GIS Cut Line= 3
      1869525.04     13981224.99      1869225.00     13981325.00
      1868775.00     13981625.00
#Sta/Elev= 30
  4683.9 2081.24  4726.1 2076.80  4768.3 2070.16  4821.0 2064.50  4852.6 2060.52
  4863.1 2059.98  4921.1 2050.90  4989.6 2042.69  4993.8 2040.13  4994.3 2039.63
  5000.8 2039.63  5001.3 2040.13  5013.7 2040.32  5043.7 2042.73  5049.7 2042.33
  5058.8 2043.47  5072.3 2043.10  5130.9 2044.76  5136.9 2044.43  5157.9 2045.13
  5230.0 2045.93  5281.1 2044.61  5288.6 2043.12  5302.1 2041.60  5311.1 2043.95
  5315.7 2044.31  5324.7 2046.80  5368.2 2050.63  5446.4 2054.56  5541.0 2056.26
#Mann=3,-1,0
  4683.9    0.07       0  4993.8    0.05       0  5001.3    0.07       0
Bank Sta=4993.8,5001.3
Exp/Cntr=0.3,0.1

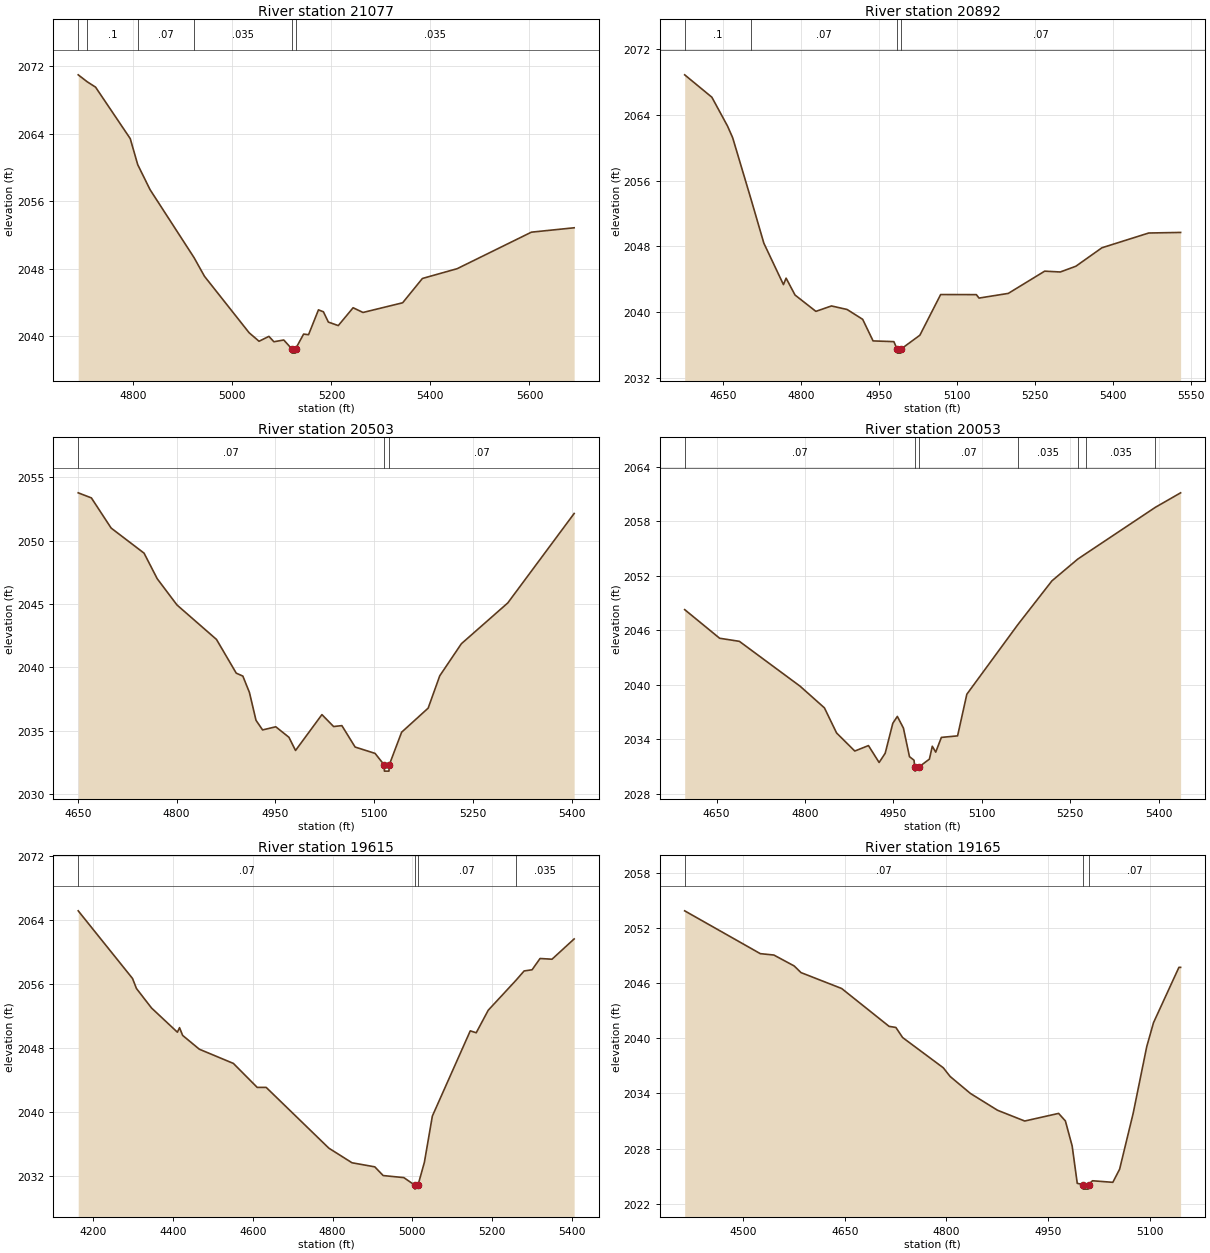
Type RM Length L Ch R = 1,21077,185,185,185
BEGIN DESCRIPTION:
West Dry Branch 46.0
END DESCRIPTION:
XS GIS Cut Line= 3
      1869380.01     13981012.57      1869081.65     13981021.47
      1868378.72     13981036.95
#Sta/Elev= 30
  4688.7 2071.01  4707.2 2070.17  4723.7 2069.55  4793.8 2063.43  4808.9 2060.34
  4833.8 2057.37  4922.6 2049.30  4943.8 2047.07  5033.9 2040.37  5053.9 2039.36
  5073.9 2039.94  5083.9 2039.30  5103.9 2039.51  5120.1 2038.45  5120.6 2037.95
  5127.1 2037.95  5127.6 2038.45  5143.9 2040.21  5153.9 2040.14  5173.9 2043.09
  5183.9 2042.86  5193.9 2041.64  5213.9 2041.22  5243.9 2043.34  5263.9 2042.78
  5343.9 2043.93  5383.9 2046.82  5454.0 2047.98  5604.0 2052.32  5690.3 2052.84
#Mann=6,-1,0
  4688.7    0.07       0  4707.2     0.1       0  4808.9    0.07       0
  4922.6   0.035       0  5120.1   0.035       0  5127.6   0.035       0
Bank Sta=5120.1,5127.6
Exp/Cntr=0.3,0.1

Type RM Length L Ch R = 1,20892,389,389,389
BEGIN DESCRIPTION:
West Dry Branch 45.2
END DESCRIPTION:
XS GIS Cut Line= 2
      1869347.27     13980955.18      1868393.61     13980929.54
#Sta/Elev= 30
  4576.7 2068.90  4629.0 2066.17  4659.0 2062.67  4669.0 2061.24  4704.8 2053.64
  4729.0 2048.38  4766.7 2043.33  4771.8 2044.12  4789.0 2042.06  4829.1 2040.07
  4859.1 2040.73  4889.1 2040.30  4919.1 2039.10  4939.1 2036.47  4979.1 2036.38
  4985.3 2035.48  4985.8 2034.98  4992.4 2034.98  4992.9 2035.48  5029.1 2037.16
  5069.1 2042.12  5137.8 2042.11  5142.9 2041.69  5199.2 2042.26  5269.2 2044.97
  5299.2 2044.87  5329.2 2045.57  5379.3 2047.82  5469.3 2049.62  5530.7 2049.69
#Mann=4,-1,0
  4576.7     0.1       0  4704.8    0.07       0  4985.3    0.05       0
  4992.9    0.07       0
Bank Sta=4985.3,4992.9
Exp/Cntr=0.3,0.1

Type RM Length L Ch R = 1,20503,450,450,450
BEGIN DESCRIPTION:
West Dry Branch 45.0
END DESCRIPTION:
XS GIS Cut Line= 3
      1869074.99     13980625.00      1868725.00     13980625.00
      1868325.00     13980675.00
#Sta/Elev= 30
  4650.5 2053.77  4670.5 2053.37  4700.5 2050.99  4750.5 2049.01  4770.5 2046.99
  4800.5 2044.92  4860.5 2042.20  4890.5 2039.54  4900.5 2039.31  4910.5 2038.02
  4920.5 2035.82  4930.5 2035.06  4950.5 2035.31  4970.5 2034.48  4980.5 2033.44
  5020.6 2036.27  5038.3 2035.33  5050.9 2035.40  5071.0 2033.71  5101.3 2033.21
  5115.0 2032.31  5115.5 2031.81  5122.4 2031.81  5122.9 2032.31  5141.6 2034.88
  5181.9 2036.78  5199.5 2039.33  5232.3 2041.86  5302.8 2045.08  5403.6 2052.14
#Mann=3,-1,0
  4650.5    0.07       0  5115.0    0.05       0  5122.9    0.07       0
Bank Sta=5115,5122.9
Exp/Cntr=0.3,0.1

Type RM Length L Ch R = 1,20053,438,438,438
BEGIN DESCRIPTION:
West Dry Branch 44.0
END DESCRIPTION:
XS GIS Cut Line= 3
      1868825.01     13980275.00      1868425.00     13980375.00
      1868055.49     13980593.11
#Sta/Elev= 30
  4595.8 2048.28  4655.1 2045.13  4688.6 2044.79  4791.7 2039.85  4832.9 2037.47
  4853.5 2034.71  4884.4 2032.72  4907.6 2033.32  4925.7 2031.46  4936.0 2032.48
  4948.9 2035.77  4956.6 2036.53  4966.9 2035.25  4977.2 2032.10  4984.9 2031.71
  4986.1 2031.01  4986.6 2030.51  4994.1 2031.01  5011.0 2031.83  5015.9 2033.25
  5021.7 2032.60  5031.3 2034.22  5058.8 2034.39  5074.5 2038.97  5160.7 2046.60
  5218.8 2051.44  5262.7 2053.84  5277.4 2054.48  5394.2 2059.53  5437.2 2061.13
#Mann=7,-1,0
  4595.8    0.07       0  4986.1    0.05       0  4994.1    0.07       0
  5160.7   0.035       0  5262.7    0.07       0  5277.4   0.035       0
  5394.2    0.07       0
Bank Sta=4986.1,4994.1
Exp/Cntr=0.3,0.1

Type RM Length L Ch R = 1,19615,450,450,450
BEGIN DESCRIPTION:
West Dry Branch 43.0
END DESCRIPTION:
XS GIS Cut Line= 3
      1869074.99     13979775.00      1868275.00     13980025.00
      1867869.58     13980038.97
#Sta/Elev= 30
  4161.8 2065.17  4298.0 2056.70  4307.9 2055.44  4345.7 2053.00  4410.6 2049.97
  4415.9 2050.54  4423.7 2049.57  4465.6 2047.84  4551.0 2046.06  4610.7 2043.06
  4633.2 2043.06  4790.4 2035.45  4848.5 2033.62  4905.6 2033.11  4926.6 2032.02
  4978.5 2031.76  5005.8 2030.82  5006.3 2030.32  5014.0 2030.82  5030.0 2033.68
  5050.0 2039.47  5145.1 2050.14  5160.0 2049.90  5190.1 2052.72  5259.7 2056.47
  5280.1 2057.64  5300.1 2057.79  5320.1 2059.20  5350.1 2059.11  5405.6 2061.65
#Mann=4,-1,0
  4161.8    0.07       0  5005.8    0.05       0  5014.0    0.07       0
  5259.7   0.035       0
Bank Sta=5005.8,5014
Exp/Cntr=0.3,0.1

Type RM Length L Ch R = 1,19165,422,422,422
BEGIN DESCRIPTION:
West Dry Branch 42.0
END DESCRIPTION:
XS GIS Cut Line= 3
      1868906.55     13979636.71      1868325.00     13979625.00
      1868174.97     13979625.00
#Sta/Elev= 30
  4413.8 2053.87  4525.4 2049.21  4545.4 2049.06  4575.4 2047.87  4585.4 2047.15
  4645.4 2045.42  4715.4 2041.30  4725.4 2041.18  4735.4 2040.08  4795.4 2036.79
  4805.4 2035.85  4835.4 2034.00  4875.4 2032.17  4915.5 2031.00  4965.5 2031.83
  4975.5 2031.01  4985.5 2028.28  4993.0 2024.22  5001.3 2024.09  5001.8 2023.59
  5009.1 2023.59  5009.6 2024.09  5015.5 2024.50  5045.5 2024.33  5055.5 2025.76
  5075.5 2031.84  5095.5 2039.09  5105.5 2041.70  5143.0 2047.72  5145.5 2047.72
#Mann=3,-1,0
  4413.8    0.07       0  5001.3    0.05       0  5009.6    0.07       0
Bank Sta=5001.3,5009.6
Exp/Cntr=0.3,0.1