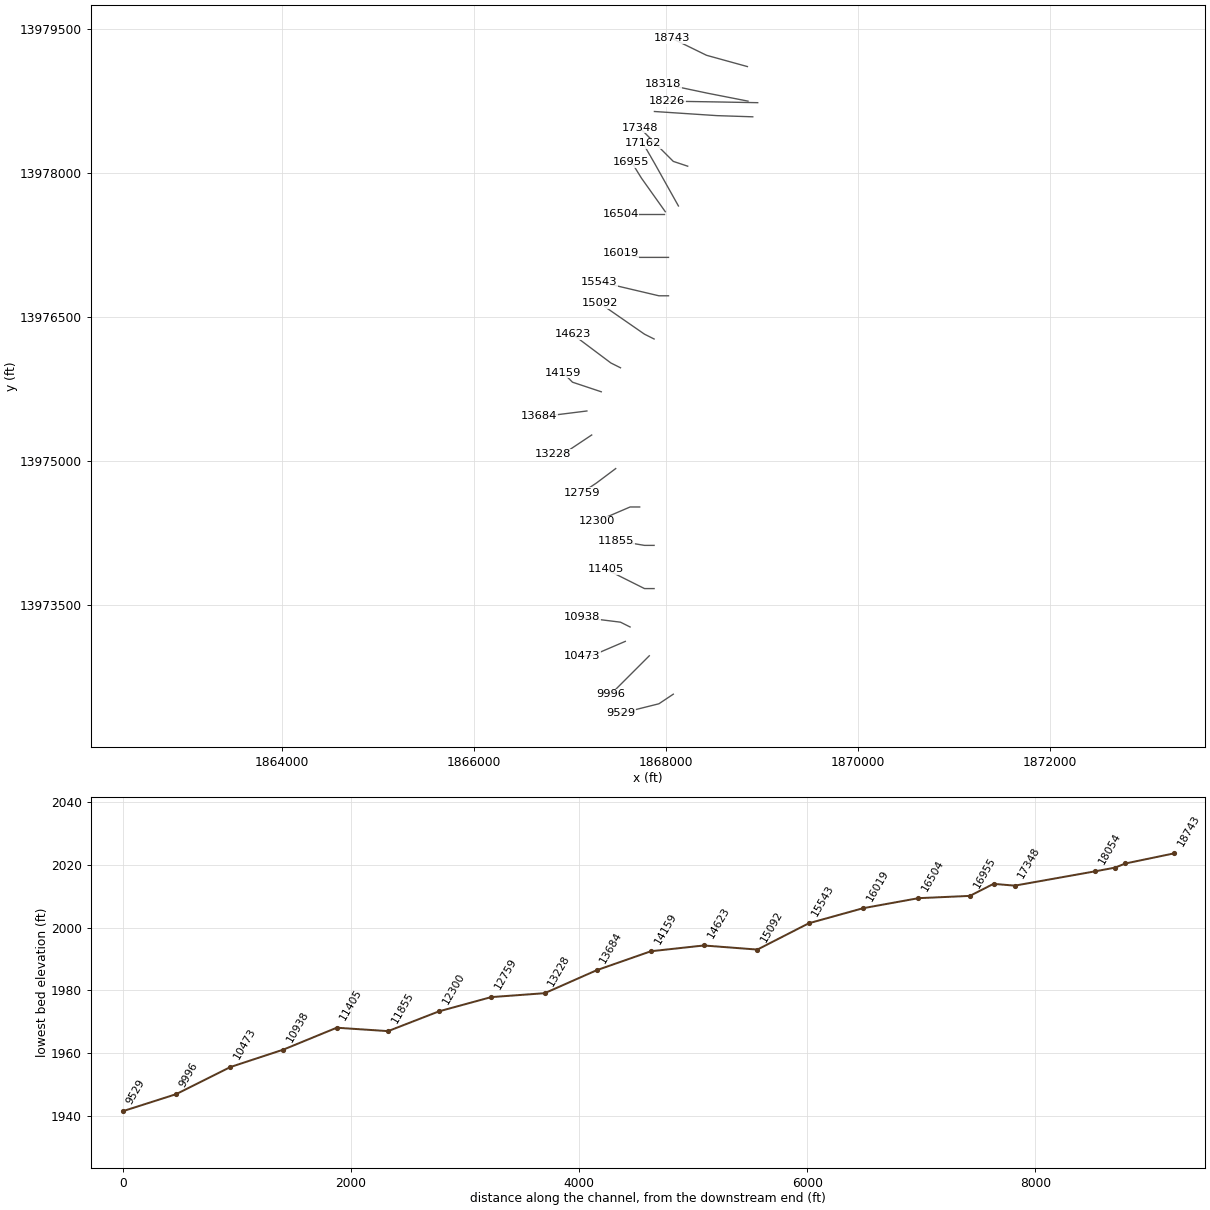
HEC-RAS study West Dry Branch.prj: West Dry Branch Base Level Engineering

--- West Dry Branch.g01 (geometry) --- (continued)

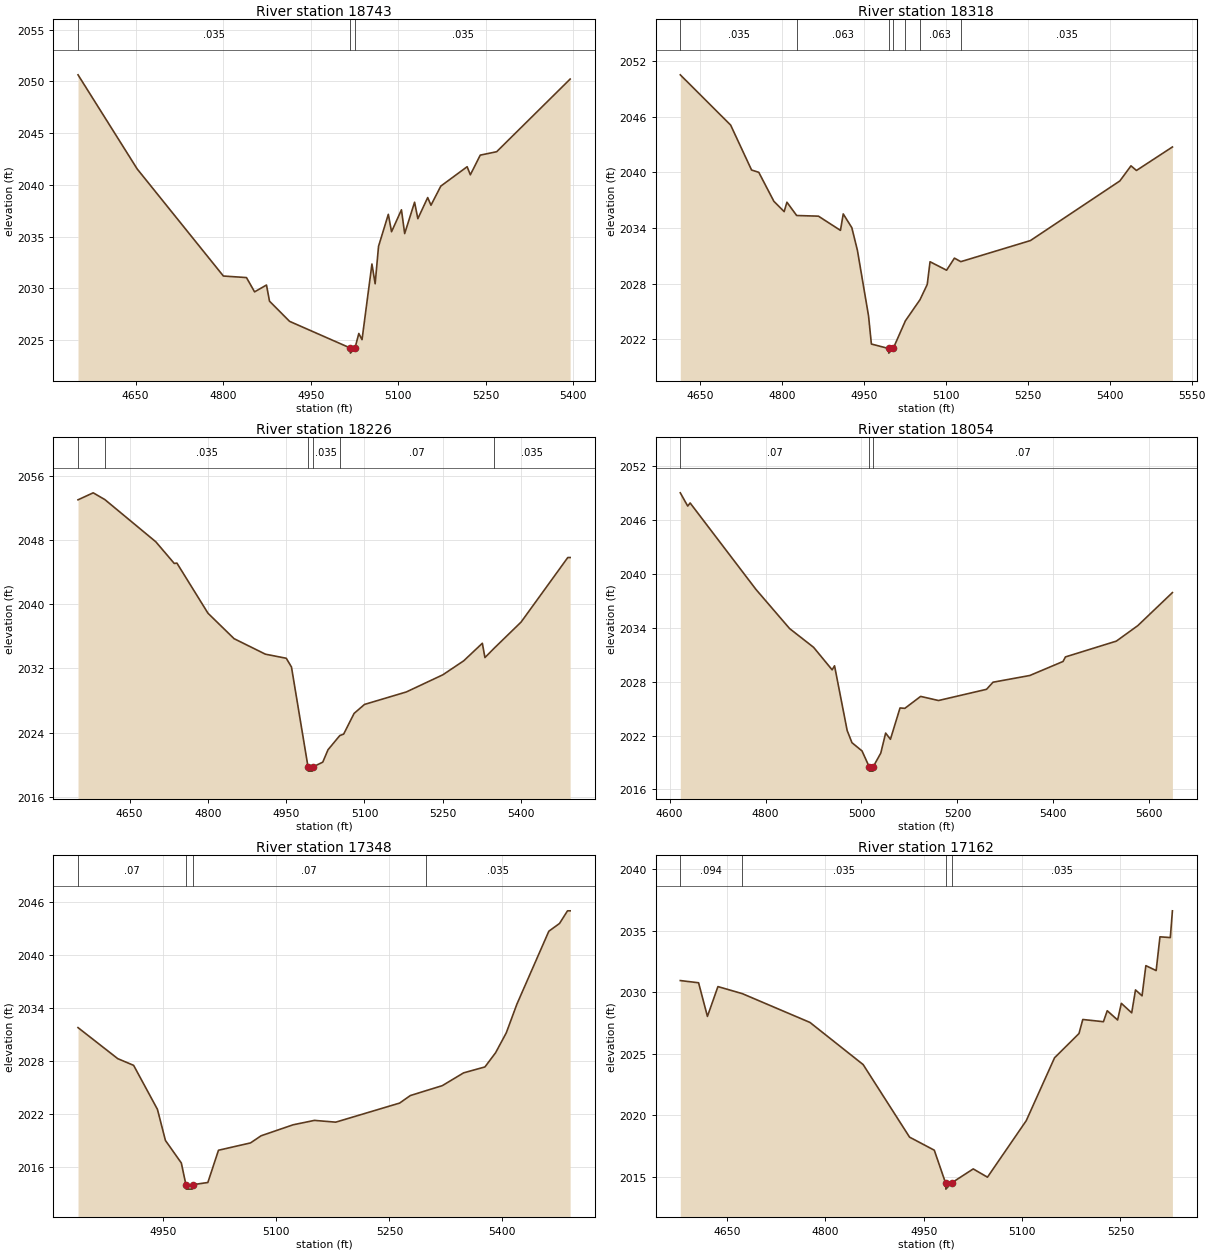
Type RM Length L Ch R = 1,18743,425,425,425
BEGIN DESCRIPTION:
West Dry Branch 41.0
END DESCRIPTION:
XS GIS Cut Line= 3
      1868846.78     13979112.69      1868421.33     13979230.19
      1868059.89     13979406.90
#Sta/Elev= 30
  4551.2 2050.63  4652.7 2041.53  4800.4 2031.19  4840.0 2031.04  4853.9 2029.66
  4874.3 2030.32  4879.5 2028.76  4913.9 2026.81  5017.7 2024.24  5018.2 2023.74
  5026.1 2024.24  5032.6 2025.64  5038.1 2025.04  5055.1 2032.35  5060.6 2030.44
  5066.4 2034.06  5083.2 2037.15  5088.7 2035.47  5105.7 2037.59  5111.2 2035.29
  5128.2 2038.32  5133.8 2036.73  5150.7 2038.77  5156.3 2038.03  5173.2 2039.88
  5218.3 2041.75  5223.8 2040.97  5240.8 2042.87  5268.9 2043.20  5394.9 2050.22
#Mann=3,-1,0
  4551.2   0.035       0  5017.7   0.035       0  5026.1   0.035       0
Bank Sta=5017.7,5026.1
Exp/Cntr=0.3,0.1

Type RM Length L Ch R = 1,18318,92,92,92
BEGIN DESCRIPTION:
West Dry Branch 40.1
END DESCRIPTION:
XS GIS Cut Line= 3
      1868852.98     13978752.80      1868432.00     13978835.21
      1867970.84     13978932.60
#Sta/Elev= 30
  4614.5 2050.49  4706.6 2045.08  4744.9 2040.24  4758.1 2039.99  4785.7 2036.87
  4804.5 2035.76  4809.6 2036.77  4827.4 2035.34  4867.2 2035.27  4907.5 2033.74
  4912.6 2035.51  4928.3 2034.03  4938.5 2031.60  4958.9 2024.53  4964.1 2021.50
  4995.4 2021.02  4995.9 2020.52  5004.0 2021.02  5026.3 2024.00  5053.1 2026.28
  5066.3 2027.92  5071.4 2030.36  5101.7 2029.45  5116.0 2030.75  5127.7 2030.37
  5255.0 2032.64  5418.6 2039.06  5439.0 2040.69  5449.0 2040.19  5514.8 2042.72
#Mann=7,-1,0
  4614.5   0.035       0  4827.4   0.063       0  4995.4    0.05       0
  5004.0   0.063       0  5026.3    0.07       0  5053.1   0.063       0
  5127.7   0.035       0
Bank Sta=4995.4,5004
Exp/Cntr=0.3,0.1

Type RM Length L Ch R = 1,18226,172,172,172
BEGIN DESCRIPTION:
West Dry Branch 40.0
END DESCRIPTION:
XS GIS Cut Line= 3
      1868954.05     13978736.63      1868507.90     13978744.77
      1868010.98     13978752.66
#Sta/Elev= 30
  4551.0 2052.99  4580.1 2053.86  4602.4 2053.02  4700.1 2047.76  4735.5 2045.06
  4740.5 2045.11  4800.1 2038.86  4850.1 2035.69  4910.1 2033.76  4950.1 2033.25
  4960.1 2032.16  4991.9 2019.69  4992.4 2019.19  5000.0 2019.19  5000.5 2019.69
  5020.1 2020.31  5030.1 2021.85  5052.7 2023.62  5060.1 2023.80  5080.1 2026.38
  5100.1 2027.50  5180.1 2029.05  5250.2 2031.19  5290.2 2032.93  5325.9 2035.12
  5330.9 2033.34  5348.7 2034.51  5400.2 2037.76  5489.7 2045.80  5494.2 2045.80
#Mann=6,-1,0
  4551.0   0.063       0  4602.4   0.035       0  4991.9   0.035       0
  5000.5   0.035       0  5052.7    0.07       0  5348.7   0.035       0
Bank Sta=4991.9,5000.5
Exp/Cntr=0.3,0.1

Type RM Length L Ch R = 1,18054,706,706,706
BEGIN DESCRIPTION:
West Dry Branch 39.0
END DESCRIPTION:
XS GIS Cut Line= 3
      1868902.75     13978589.40      1868528.13     13978601.80
      1867878.37     13978644.78
#Sta/Elev= 30
  4622.3 2049.05  4637.8 2047.57  4642.8 2047.92  4780.1 2038.28  4850.2 2033.92
  4900.2 2031.83  4938.9 2029.32  4943.9 2029.77  4970.2 2022.56  4980.2 2021.20
  5001.2 2020.28  5016.0 2018.53  5016.5 2018.03  5024.1 2018.03  5024.6 2018.53
  5040.3 2020.04  5050.4 2022.27  5060.4 2021.58  5080.4 2025.07  5090.5 2025.03
  5123.4 2026.36  5160.6 2025.90  5260.8 2027.15  5274.3 2027.94  5351.0 2028.69
  5420.2 2030.25  5425.3 2030.76  5531.4 2032.52  5576.2 2034.25  5648.3 2037.93
#Mann=3,-1,0
  4622.3    0.07       0  5016.0    0.05       0  5024.6    0.07       0
Bank Sta=5016,5024.6
Exp/Cntr=0.3,0.1

Type RM Length L Ch R = 1,17348,186,186,186
BEGIN DESCRIPTION:
West Dry Branch 38.0
END DESCRIPTION:
XS GIS Cut Line= 3
      1868225.03     13978074.99      1868075.00     13978125.00
      1867725.02     13978474.98
#Sta/Elev= 30
  4836.8 2031.73  4889.5 2028.22  4910.6 2027.46  4942.2 2022.48  4952.8 2018.96
  4973.9 2016.41  4980.0 2013.95  4980.5 2013.45  4988.3 2013.45  4988.8 2013.95
  5009.1 2014.20  5023.2 2017.85  5065.7 2018.68  5079.8 2019.49  5122.2 2020.73
  5150.5 2021.23  5178.8 2021.03  5263.6 2023.19  5277.8 2024.04  5298.1 2024.58
  5320.2 2025.16  5348.5 2026.61  5376.8 2027.28  5390.9 2028.88  5405.1 2031.13
  5419.2 2034.38  5461.6 2042.64  5475.8 2043.52  5486.4 2044.95  5489.9 2044.95
#Mann=4,-1,0
  4836.8    0.07       0  4980.0    0.05       0  4988.8    0.07       0
  5298.1   0.035       0
Bank Sta=4980,4988.8
Exp/Cntr=0.3,0.1

Type RM Length L Ch R = 1,17162,207,207,207
BEGIN DESCRIPTION:
West Dry Branch 37.1
END DESCRIPTION:
XS GIS Cut Line= 3
      1868128.43     13977660.69      1867880.34     13978104.28
      1867759.18     13978314.16
#Sta/Elev= 30
  4578.7 2030.95  4606.6 2030.77  4620.1 2028.04  4636.1 2030.46  4673.2 2029.89
  4776.5 2027.55  4857.6 2024.13  4928.4 2018.24  4966.1 2017.18  4983.3 2014.52
  4983.8 2014.02  4992.4 2014.52  5025.5 2015.66  5047.2 2014.99  5106.4 2019.58
  5149.5 2024.68  5186.8 2026.65  5192.6 2027.79  5224.1 2027.61  5229.9 2028.50
  5245.7 2027.75  5251.4 2029.10  5267.2 2028.33  5273.0 2030.19  5283.0 2029.71
  5288.8 2032.16  5304.5 2031.76  5310.3 2034.50  5326.1 2034.44  5329.3 2036.61
#Mann=4,-1,0
  4578.7   0.094       0  4673.2   0.035       0  4983.3   0.035       0
  4992.4   0.035       0
Bank Sta=4983.3,4992.4
Exp/Cntr=0.3,0.1

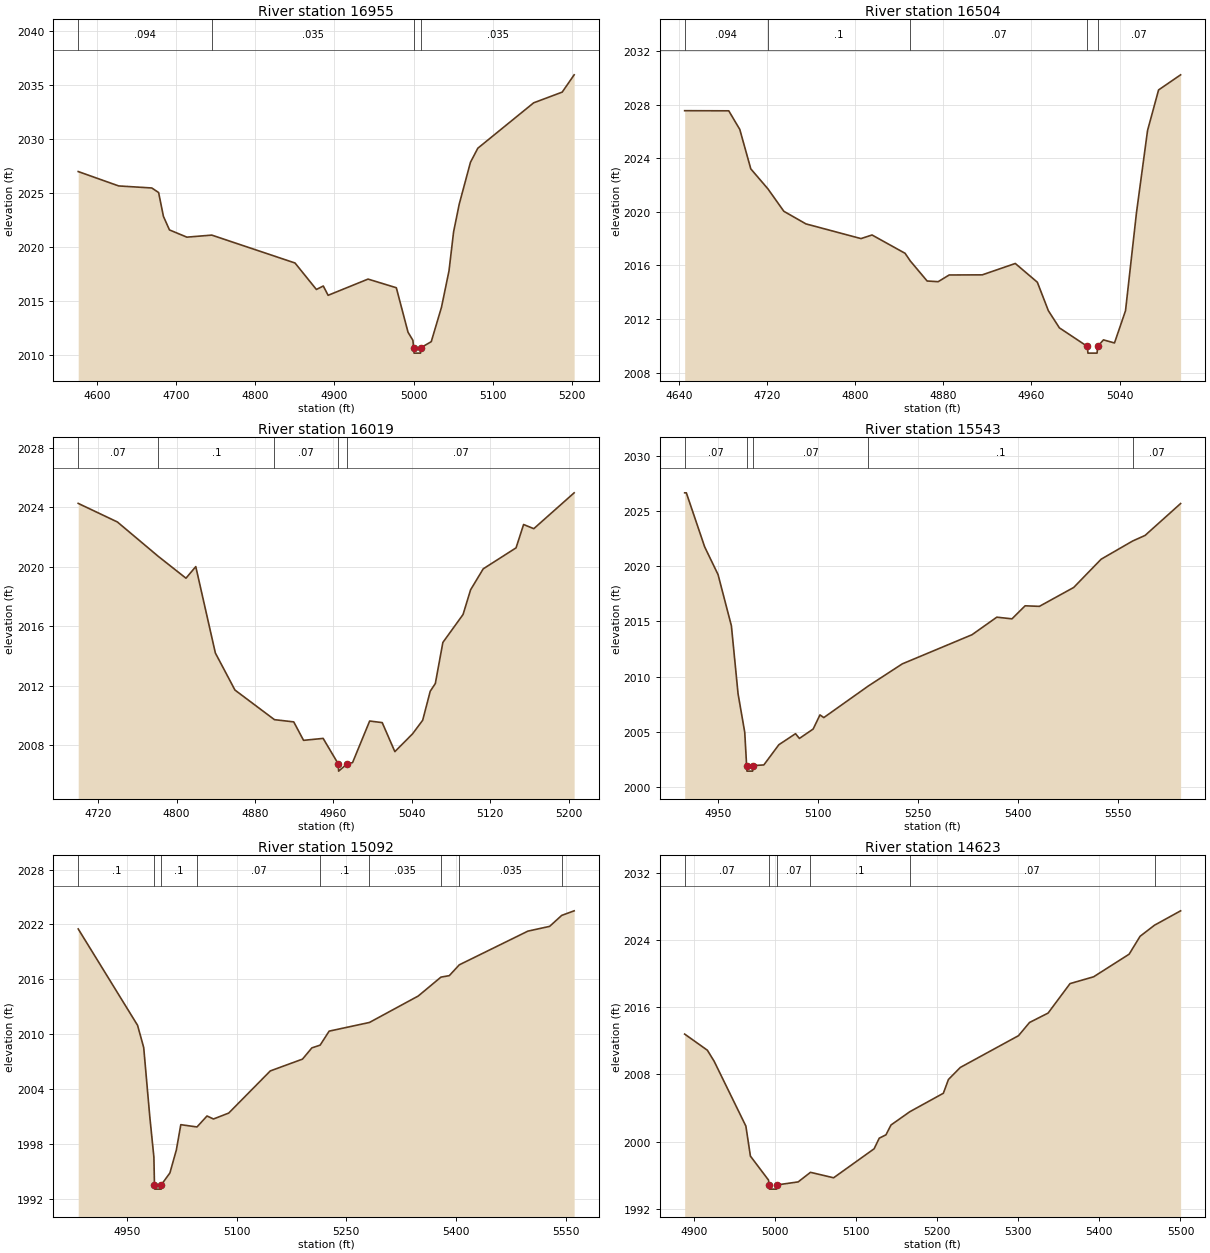
Type RM Length L Ch R = 1,16955,451,451,451
BEGIN DESCRIPTION:
West Dry Branch 37.0
END DESCRIPTION:
XS GIS Cut Line= 3
      1867991.52     13977601.10      1867743.52     13977950.12
      1867639.31     13978118.40
#Sta/Elev= 30
  4576.5 2026.98  4627.6 2025.65  4669.4 2025.46  4678.0 2025.04  4684.1 2022.83
  4691.7 2021.58  4713.7 2020.91  4745.1 2021.10  4850.2 2018.52  4877.2 2016.07
  4885.9 2016.39  4892.0 2015.53  4942.4 2017.03  4978.1 2016.23  4992.9 2012.11
  4999.0 2011.37  5000.0 2010.68  5000.5 2010.18  5008.6 2010.18  5009.1 2010.68
  5022.2 2011.24  5035.1 2014.42  5044.6 2017.79  5050.4 2021.40  5057.5 2023.96
  5071.7 2027.84  5081.0 2029.14  5151.5 2033.34  5187.5 2034.33  5202.6 2035.93
#Mann=4,-1,0
  4576.5   0.094       0  4745.1   0.035       0  5000.0   0.035       0
  5009.1   0.035       0
Bank Sta=5000,5009.1
Exp/Cntr=0.3,0.1

Type RM Length L Ch R = 1,16504,485,485,485
BEGIN DESCRIPTION:
West Dry Branch 36.0
END DESCRIPTION:
XS GIS Cut Line= 3
      1867975.03     13977575.00      1867625.00     13977575.00
      1867525.03     13977575.00
#Sta/Elev= 30
  4645.4 2027.57  4685.4 2027.56  4695.4 2026.17  4705.4 2023.22  4720.9 2021.73
  4735.4 2020.05  4755.4 2019.11  4805.4 2018.01  4815.4 2018.28  4845.4 2016.91
  4850.1 2016.34  4865.4 2014.84  4875.4 2014.79  4885.4 2015.29  4915.4 2015.30
  4945.4 2016.15  4965.4 2014.75  4975.4 2012.62  4985.4 2011.34  5010.8 2009.95
  5011.3 2009.45  5019.6 2009.45  5020.1 2009.95  5025.4 2010.44  5035.4 2010.21
  5045.4 2012.62  5055.4 2019.98  5065.4 2026.09  5075.4 2029.12  5095.4 2030.25
#Mann=5,-1,0
  4645.4   0.094       0  4720.9     0.1       0  4850.1    0.07       0
  5010.8    0.05       0  5020.1    0.07       0
Bank Sta=5010.8,5020.1
Exp/Cntr=0.3,0.1

Type RM Length L Ch R = 1,16019,476,476,476
BEGIN DESCRIPTION:
West Dry Branch 35.0
END DESCRIPTION:
XS GIS Cut Line= 3
      1868025.03     13977125.00      1867725.00     13977125.00
      1867524.99     13977175.00
#Sta/Elev= 30
  4699.5 2024.25  4739.5 2023.00  4781.2 2020.69  4809.5 2019.22  4819.5 2020.00
  4839.5 2014.19  4859.5 2011.70  4899.8 2009.71  4919.5 2009.56  4929.5 2008.32
  4949.5 2008.45  4964.8 2006.75  4965.3 2006.25  4974.2 2006.75  4979.5 2006.82
  4997.0 2009.62  5009.8 2009.51  5022.7 2007.56  5040.8 2008.76  5051.1 2009.67
  5058.8 2011.62  5064.0 2012.14  5071.7 2014.90  5092.3 2016.78  5100.0 2018.44
  5112.9 2019.85  5146.4 2021.26  5154.1 2022.83  5164.5 2022.55  5205.7 2024.96
#Mann=5,-1,0
  4699.5    0.07       0  4781.2     0.1       0  4899.8    0.07       0
  4964.8    0.05       0  4974.2    0.07       0
Bank Sta=4964.8,4974.2
Exp/Cntr=0.3,0.1

Type RM Length L Ch R = 1,15543,451,451,451
BEGIN DESCRIPTION:
West Dry Branch 34.0
END DESCRIPTION:
XS GIS Cut Line= 3
      1868025.01     13976725.00      1867925.00     13976725.00
      1867299.05     13976872.45
#Sta/Elev= 30
  4900.1 2026.64  4902.6 2026.64  4930.1 2021.74  4950.1 2019.24  4970.1 2014.60
  4980.1 2008.44  4990.1 2004.96  4992.9 2001.94  4993.4 2001.44  5001.9 2001.44
  5002.4 2001.94  5018.7 2002.00  5041.2 2003.83  5066.2 2004.83  5072.0 2004.40
  5092.6 2005.25  5102.8 2006.53  5108.6 2006.29  5175.3 2009.15  5226.1 2011.15
  5330.6 2013.79  5367.8 2015.38  5390.5 2015.23  5410.2 2016.41  5431.6 2016.36
  5483.0 2018.07  5524.1 2020.63  5571.4 2022.28  5589.9 2022.78  5643.2 2025.67
#Mann=5,-1,0
  4900.1    0.07       0  4992.9    0.05       0  5002.4    0.07       0
  5175.3     0.1       0  5571.4    0.07       0
Bank Sta=4992.9,5002.4
Exp/Cntr=0.3,0.1

Type RM Length L Ch R = 1,15092,469,469,469
BEGIN DESCRIPTION:
West Dry Branch 33.0
END DESCRIPTION:
XS GIS Cut Line= 3
      1867875.02     13976274.99      1867775.00     13976325.00
      1867309.80     13976647.19
#Sta/Elev= 30
  4883.7 2021.50  4964.8 2010.96  4973.2 2008.53  4981.5 2000.98  4987.1 1996.55
  4987.9 1993.54  4988.4 1993.04  4997.0 1993.04  4997.5 1993.54  5009.0 1994.81
  5017.8 1997.32  5023.9 2000.09  5046.0 1999.84  5059.7 2001.04  5068.5 2000.71
  5089.4 2001.36  5146.2 2005.97  5190.2 2007.26  5203.0 2008.49  5214.3 2008.79
  5226.6 2010.32  5281.7 2011.27  5348.3 2014.16  5379.4 2016.23  5390.8 2016.39
  5404.4 2017.57  5498.2 2021.26  5527.9 2021.78  5544.4 2022.98  5561.4 2023.48
#Mann=9,-1,0
  4883.7     0.1       0  4987.9    0.05       0  4997.5     0.1       0
  5046.0    0.07       0  5214.3     0.1       0  5281.7   0.035       0
  5379.4     0.1       0  5404.4   0.035       0  5544.4    0.07       0
Bank Sta=4987.9,4997.5
Exp/Cntr=0.3,0.1

Type RM Length L Ch R = 1,14623,464,464,464
BEGIN DESCRIPTION:
West Dry Branch 32.0
END DESCRIPTION:
XS GIS Cut Line= 3
      1867525.03     13975974.99      1867425.00     13976025.00
      1867025.03     13976324.98
#Sta/Elev= 30
  4888.4 2012.80  4916.4 2010.88  4924.8 2009.56  4963.9 2001.85  4969.5 1998.28
  4991.8 1995.43  4992.6 1994.85  4993.1 1994.35  5001.7 1994.35  5002.2 1994.85
  5028.4 1995.21  5043.6 1996.35  5072.1 1995.70  5122.1 1999.15  5128.4 2000.41
  5136.7 2000.81  5142.9 2001.98  5166.1 2003.56  5207.5 2005.76  5213.8 2007.40
  5228.4 2008.83  5300.2 2012.61  5313.8 2014.18  5336.7 2015.30  5363.8 2018.81
  5392.9 2019.62  5436.7 2022.31  5450.2 2024.44  5468.0 2025.76  5500.2 2027.47
#Mann=6,-1,0
  4888.4    0.07       0  4992.6    0.05       0  5002.2    0.07       0
  5043.6     0.1       0  5166.1    0.07       0  5468.0   0.035       0
Bank Sta=4992.6,5002.2
Exp/Cntr=0.3,0.1

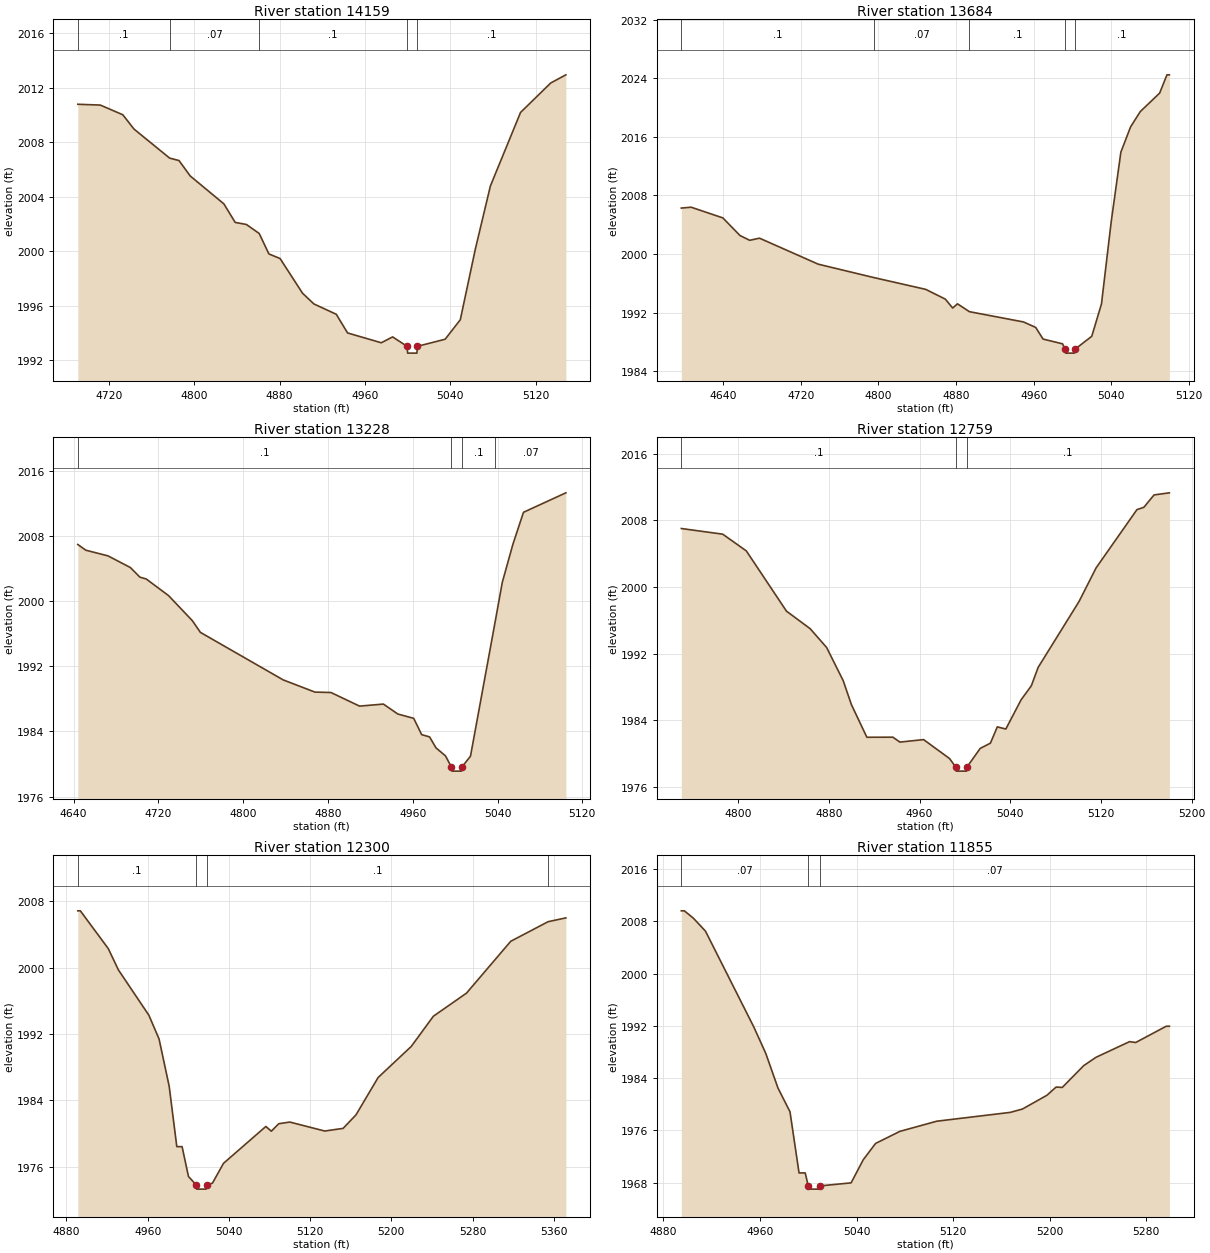
Type RM Length L Ch R = 1,14159,475,475,475
BEGIN DESCRIPTION:
West Dry Branch 31.0
END DESCRIPTION:
XS GIS Cut Line= 3
      1867325.01     13975725.00      1867025.00     13975825.00
      1866924.97     13975925.03
#Sta/Elev= 30
  4690.7 2010.77  4711.8 2010.71  4732.9 2010.00  4743.4 2008.95  4776.8 2006.82
  4785.6 2006.64  4796.1 2005.51  4827.7 2003.46  4838.3 2002.10  4848.8 2001.95
  4860.8 2001.29  4869.9 1999.79  4880.4 1999.45  4901.5 1996.90  4912.1 1996.12
  4933.1 1995.36  4943.7 1993.99  4975.3 1993.27  4985.9 1993.70  4999.5 1993.01
  5000.0 1992.51  5008.7 1992.51  5009.2 1993.01  5035.2 1993.53  5049.4 1994.96
  5063.5 2000.14  5077.6 2004.77  5105.9 2010.17  5134.2 2012.33  5148.4 2012.93
#Mann=5,-1,0
  4690.7     0.1       0  4776.8    0.07       0  4860.8     0.1       0
  4999.5    0.05       0  5009.2     0.1       0
Bank Sta=4999.5,5009.2
Exp/Cntr=0.3,0.1

Type RM Length L Ch R = 1,13684,456,456,456
BEGIN DESCRIPTION:
West Dry Branch 30.0
END DESCRIPTION:
XS GIS Cut Line= 3
      1867175.00     13975525.00      1866775.00     13975475.00
      1866675.01     13975475.00
#Sta/Elev= 30
  4596.8 2006.27  4606.9 2006.39  4639.6 2004.93  4657.3 2002.52  4667.3 2001.87
  4677.4 2002.16  4737.9 1998.61  4794.9 1996.79  4848.7 1995.17  4868.9 1993.84
  4876.5 1992.62  4881.5 1993.19  4893.8 1992.12  4949.5 1990.72  4962.1 1989.97
  4969.7 1988.38  4989.8 1987.73  4992.5 1986.96  4993.0 1986.46  5001.8 1986.46
  5002.3 1986.96  5019.9 1988.76  5029.9 1993.18  5039.9 2004.37  5049.9 2013.91
  5059.9 2017.36  5069.9 2019.45  5089.9 2021.98  5097.4 2024.47  5099.9 2024.47
#Mann=5,-1,0
  4596.8     0.1       0  4794.9    0.07       0  4893.8     0.1       0
  4992.5    0.05       0  5002.3     0.1       0
Bank Sta=4992.5,5002.3
Exp/Cntr=0.3,0.1

Type RM Length L Ch R = 1,13228,469,469,469
BEGIN DESCRIPTION:
West Dry Branch 29.0
END DESCRIPTION:
XS GIS Cut Line= 3
      1867225.00     13975275.00      1866925.00     13975075.00
      1866824.95     13975075.00
#Sta/Elev= 30
  4643.9 2006.94  4651.4 2006.24  4672.4 2005.54  4693.5 2004.11  4702.5 2002.93
  4708.5 2002.70  4729.5 2000.67  4752.1 1997.57  4759.6 1996.15  4837.7 1990.32
  4867.7 1988.82  4882.8 1988.77  4909.8 1987.10  4932.3 1987.35  4945.9 1986.13
  4960.9 1985.60  4968.4 1983.60  4975.9 1983.32  4981.9 1981.98  4990.9 1980.99
  4996.5 1979.62  4997.0 1979.12  5005.9 1979.12  5006.4 1979.62  5014.5 1980.96
  5038.0 1997.62  5044.5 2002.29  5054.5 2006.96  5064.5 2010.89  5104.5 2013.28
#Mann=4,-1,0
  4643.9     0.1       0  4996.5    0.05       0  5006.4     0.1       0
  5038.0    0.07       0
Bank Sta=4996.5,5006.4
Exp/Cntr=0.3,0.1

Type RM Length L Ch R = 1,12759,459,459,459
BEGIN DESCRIPTION:
West Dry Branch 28.0
END DESCRIPTION:
XS GIS Cut Line= 3
      1867475.01     13974925.01      1867275.00     13974775.00
      1867124.99     13974674.99
#Sta/Elev= 30
  4750.0 2007.03  4786.5 2006.35  4807.3 2004.34  4842.7 1997.10  4863.6 1994.99
  4878.1 1992.73  4892.7 1988.75  4900.0 1985.85  4913.6 1981.94  4936.5 1981.95
  4942.7 1981.36  4963.6 1981.66  4986.5 1979.38  4991.9 1978.37  4992.4 1977.87
  5001.4 1977.87  5001.9 1978.37  5013.5 1980.60  5022.5 1981.23  5028.6 1983.19
  5036.1 1982.93  5049.6 1986.45  5058.6 1988.13  5064.6 1990.34  5100.7 1998.27
  5115.7 2002.30  5151.7 2009.30  5157.8 2009.58  5166.8 2011.07  5180.3 2011.32
#Mann=3,-1,0
  4750.0     0.1       0  4991.9    0.05       0  5001.9     0.1       0
Bank Sta=4991.9,5001.9
Exp/Cntr=0.3,0.1

Type RM Length L Ch R = 1,12300,445,445,445
BEGIN DESCRIPTION:
West Dry Branch 27.0
END DESCRIPTION:
XS GIS Cut Line= 3
      1867724.96     13974525.00      1867625.00     13974525.00
      1867275.04     13974375.02
#Sta/Elev= 30
  4891.2 2006.84  4893.7 2006.84  4921.2 2002.29  4931.2 1999.72  4961.2 1994.26
  4971.2 1991.41  4981.2 1985.70  4988.7 1978.43  4993.9 1978.43  5000.2 1974.83
  5007.9 1973.81  5008.4 1973.31  5017.5 1973.31  5018.0 1973.81  5023.8 1974.03
  5034.7 1976.42  5076.4 1980.86  5081.8 1980.29  5089.1 1981.19  5100.0 1981.39
  5134.4 1980.31  5152.5 1980.63  5165.2 1982.26  5187.0 1986.76  5219.6 1990.50
  5241.4 1994.14  5274.0 1996.92  5317.6 2003.17  5354.4 2005.53  5371.9 2005.99
#Mann=4,-1,0
  4891.2     0.1       0  5007.9    0.05       0  5018.0     0.1       0
  5354.4    0.07       0
Bank Sta=5007.9,5018
Exp/Cntr=0.3,0.1

Type RM Length L Ch R = 1,11855,450,450,450
BEGIN DESCRIPTION:
West Dry Branch 26.0
END DESCRIPTION:
XS GIS Cut Line= 3
      1867875.05     13974125.00      1867775.00     13974125.00
      1867474.98     13974175.00
#Sta/Elev= 30
  4894.9 2009.62  4897.4 2009.62  4904.9 2008.49  4914.9 2006.51  4954.9 1991.85
  4964.9 1987.76  4974.9 1982.51  4984.9 1978.85  4992.4 1969.49  4997.5 1969.49
  5000.0 1967.51  5000.5 1967.01  5009.6 1967.01  5010.1 1967.51  5035.5 1967.97
  5045.6 1971.52  5055.8 1974.01  5076.0 1975.86  5106.5 1977.41  5167.3 1978.76
  5177.4 1979.27  5197.7 1981.38  5205.3 1982.64  5210.4 1982.58  5228.1 1985.91
  5238.3 1987.19  5266.1 1989.59  5271.2 1989.46  5296.5 1991.95  5299.1 1991.95
#Mann=3,-1,0
  4894.9    0.07       0  5000.0    0.05       0  5010.1    0.07       0
Bank Sta=5000,5010.1
Exp/Cntr=0.3,0.1

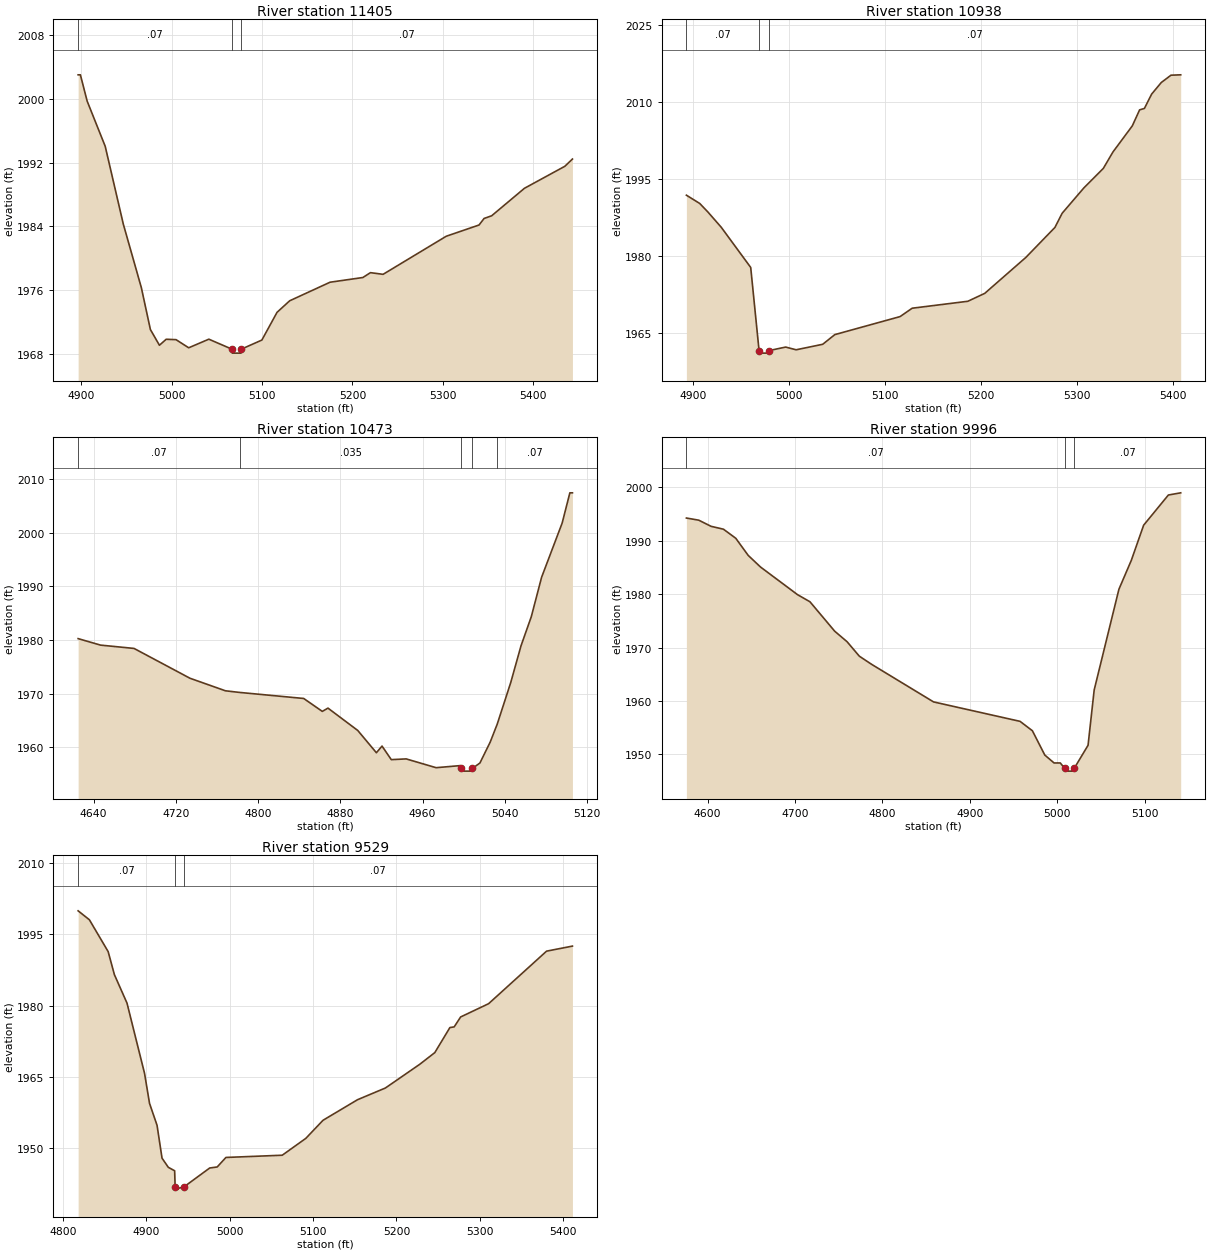
Type RM Length L Ch R = 1,11405,467,467,467
BEGIN DESCRIPTION:
West Dry Branch 25.0
END DESCRIPTION:
XS GIS Cut Line= 3
      1867875.00     13973675.00      1867775.00     13973675.00
      1867375.01     13973875.00
#Sta/Elev= 30
  4896.3 2003.03  4898.8 2003.03  4906.3 1999.73  4926.3 1994.05  4946.3 1984.30
  4966.3 1976.31  4976.3 1971.06  4986.3 1969.09  4993.8 1969.84  5004.7 1969.79
  5018.7 1968.77  5041.0 1969.85  5066.5 1968.60  5067.0 1968.10  5076.5 1968.10
  5077.0 1968.60  5099.7 1969.74  5116.5 1973.22  5130.5 1974.67  5175.2 1977.00
  5211.5 1977.59  5219.9 1978.20  5233.9 1977.99  5303.8 1982.77  5340.1 1984.18
  5345.7 1985.00  5354.1 1985.34  5390.4 1988.79  5435.1 1991.55  5443.5 1992.46
#Mann=3,-1,0
  4896.3    0.07       0  5066.5    0.05       0  5077.0    0.07       0
Bank Sta=5066.5,5077
Exp/Cntr=0.3,0.1

Type RM Length L Ch R = 1,10938,465,465,465
BEGIN DESCRIPTION:
West Dry Branch 24.0
END DESCRIPTION:
XS GIS Cut Line= 3
      1867624.97     13973275.02      1867525.00     13973325.00
      1867124.98     13973375.00
#Sta/Elev= 30
  4892.8 1991.85  4906.7 1990.24  4915.1 1988.60  4929.1 1985.61  4959.8 1977.79
  4968.5 1961.62  4969.0 1961.12  4978.6 1961.12  4979.1 1961.62  4996.2 1962.30
  5007.1 1961.77  5034.8 1962.84  5047.4 1964.72  5115.4 1968.23  5128.0 1969.86
  5186.0 1971.21  5203.6 1972.75  5246.4 1979.74  5276.7 1985.58  5284.2 1988.33
  5306.9 1993.28  5327.1 1997.06  5337.1 2000.25  5357.3 2005.34  5364.9 2008.45
  5369.9 2008.73  5377.4 2011.51  5387.5 2013.78  5397.6 2015.20  5407.7 2015.27
#Mann=3,-1,0
  4892.8    0.07       0  4968.5    0.05       0  4979.1    0.07       0
Bank Sta=4968.5,4979.1
Exp/Cntr=0.3,0.1

Type RM Length L Ch R = 1,10473,477,477,477
BEGIN DESCRIPTION:
West Dry Branch 23.0
END DESCRIPTION:
XS GIS Cut Line= 3
      1867575.00     13973125.00      1867225.00     13972975.00
      1867124.99     13972975.00
#Sta/Elev= 30
  4625.0 1980.26  4646.8 1979.05  4679.4 1978.43  4733.8 1972.87  4768.3 1970.53
  4782.4 1970.22  4844.4 1969.10  4862.5 1966.69  4868.0 1967.30  4897.0 1963.13
  4915.1 1958.98  4920.6 1960.22  4929.6 1957.69  4944.1 1957.83  4973.2 1956.19
  4996.7 1956.58  4997.8 1956.05  4998.3 1955.55  5007.9 1955.55  5008.4 1956.05
  5015.8 1957.06  5025.8 1960.96  5032.6 1964.29  5045.8 1972.08  5055.8 1978.93
  5065.8 1984.36  5075.8 1991.70  5095.8 2001.81  5103.3 2007.45  5105.8 2007.45
#Mann=5,-1,0
  4625.0    0.07       0  4782.4   0.035       0  4997.8   0.035       0
  5008.4   0.035       0  5032.6    0.07       0
Bank Sta=4997.8,5008.4
Exp/Cntr=0.3,0.1

Type RM Length L Ch R = 1,9996,467,467,467
BEGIN DESCRIPTION:
West Dry Branch 22.0
END DESCRIPTION:
XS GIS Cut Line= 3
      1867824.97     13972974.97      1867525.00     13972675.00
      1867425.03     13972575.03
#Sta/Elev= 30
  4575.8 1994.26  4589.9 1993.86  4604.0 1992.71  4618.2 1992.17  4632.3 1990.47
  4646.5 1987.27  4660.6 1985.09  4703.0 1979.91  4717.2 1978.58  4745.5 1973.07
  4759.6 1971.11  4773.7 1968.39  4787.9 1966.85  4858.6 1959.83  4957.6 1956.19
  4971.7 1954.43  4985.9 1949.88  4996.5 1948.40  5003.6 1948.40  5008.8 1947.37
  5009.3 1946.87  5019.0 1946.87  5019.5 1947.37  5035.4 1951.71  5042.4 1962.06
  5070.7 1980.92  5084.9 1986.34  5099.0 1992.92  5127.3 1998.57  5141.4 1998.98
#Mann=3,-1,0
  4575.8    0.07       0  5008.8    0.05       0  5019.5    0.07       0
Bank Sta=5008.8,5019.5
Exp/Cntr=0.3,0.1

Type RM Length L Ch R = 1,9529,465,465,465
BEGIN DESCRIPTION:
West Dry Branch 21.0
END DESCRIPTION:
XS GIS Cut Line= 3
      1868074.98     13972574.99      1867925.00     13972475.00
      1867524.96     13972374.99
#Sta/Elev= 30
  4818.4 1999.97  4831.9 1998.09  4854.4 1991.39  4861.9 1986.54  4877.0 1980.56
  4898.0 1965.81  4904.0 1959.48  4913.0 1954.87  4919.0 1947.95  4926.5 1946.03
  4934.1 1945.30  4934.7 1941.94  4935.2 1941.44  4945.5 1941.94  4976.1 1945.88
  4985.1 1946.10  4995.6 1948.10  5063.1 1948.57  5091.4 1952.12  5112.0 1955.92
  5153.3 1960.24  5186.8 1962.71  5228.0 1967.70  5246.0 1970.15  5264.1 1975.42
  5269.2 1975.56  5277.0 1977.65  5310.5 1980.44  5380.0 1991.49  5411.0 1992.55
#Mann=3,-1,0
  4818.4    0.07       0  4934.7    0.05       0  4945.5    0.07       0
Bank Sta=4934.7,4945.5
Exp/Cntr=0.3,0.1