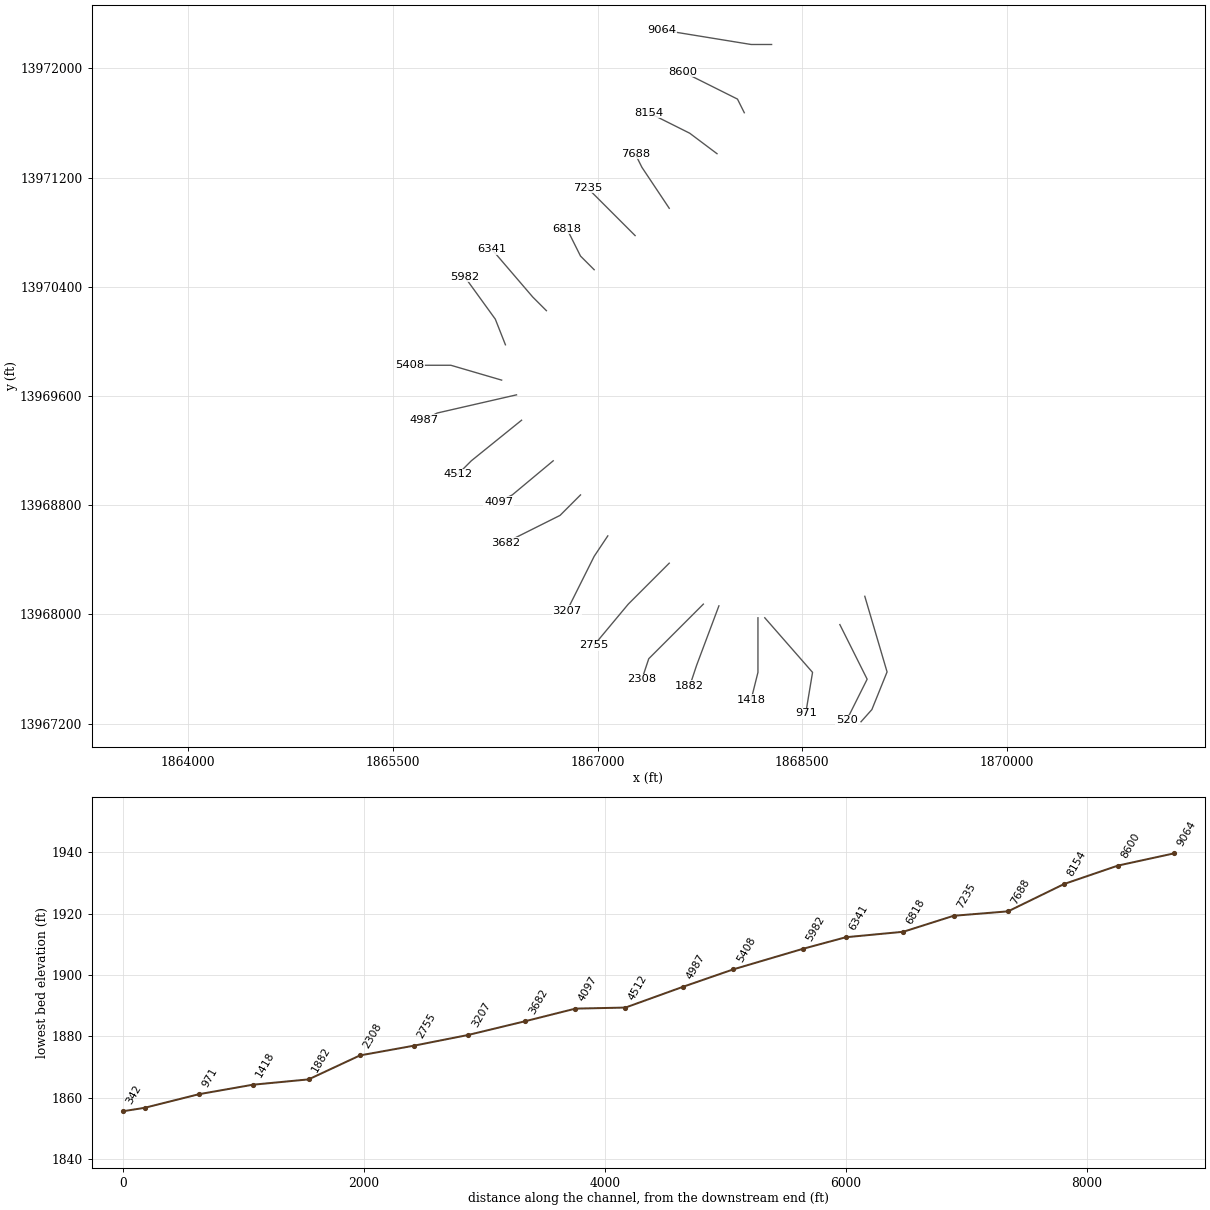
HEC-RAS study West Dry Branch.prj: West Dry Branch Base Level Engineering

--- West Dry Branch.g01 (geometry) --- (continued)

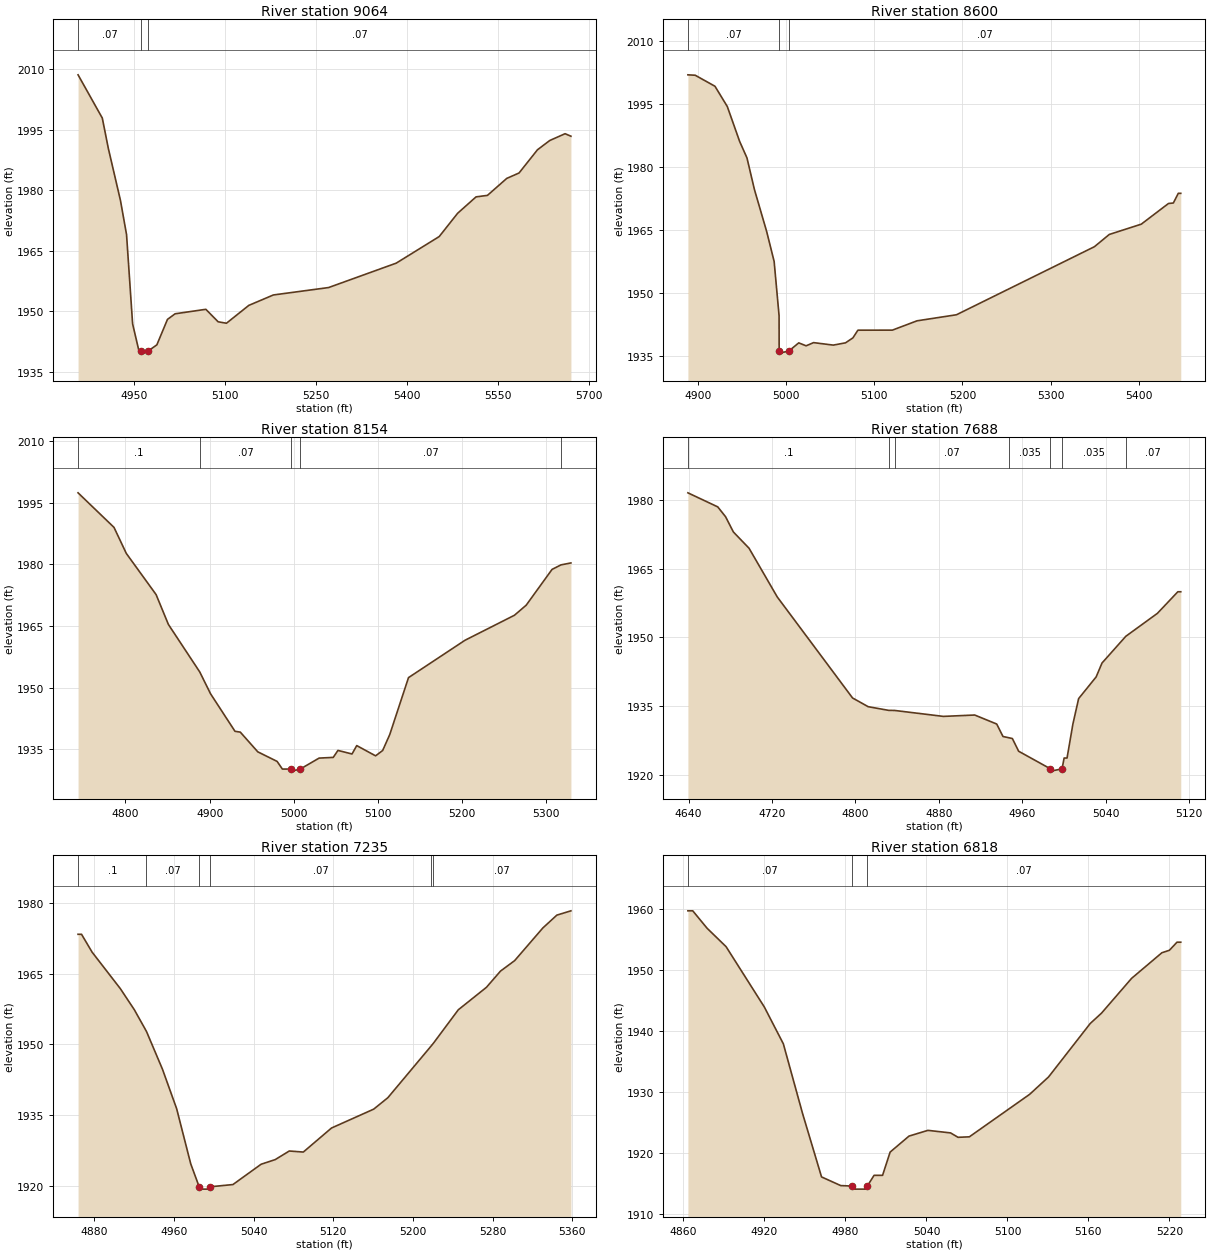
Type RM Length L Ch R = 1,9064,464,464,464
BEGIN DESCRIPTION:
West Dry Branch 20.0
END DESCRIPTION:
XS GIS Cut Line= 3
      1868275.01     13972175.00      1868125.00     13972175.00
      1867470.52     13972281.53
#Sta/Elev= 30
  4857.8 2008.54  4897.8 1997.83  4907.8 1990.29  4927.8 1977.41  4937.8 1968.97
  4947.8 1946.87  4957.8 1940.47  4962.4 1940.13  4962.9 1939.63  4973.3 1940.13
  4987.8 1941.68  5005.3 1947.98  5017.9 1949.37  5068.6 1950.48  5088.9 1947.39
  5102.6 1947.03  5139.5 1951.45  5180.0 1954.03  5271.2 1955.87  5382.7 1961.91
  5453.6 1968.49  5484.0 1974.26  5514.4 1978.32  5533.2 1978.69  5565.0 1982.89
  5585.3 1984.23  5615.7 1989.98  5636.0 1992.28  5661.3 1993.96  5670.9 1993.34
#Mann=3,-1,0
  4857.8    0.07       0  4962.4    0.05       0  4973.3    0.07       0
Bank Sta=4962.4,4973.3
Exp/Cntr=0.3,0.1

Type RM Length L Ch R = 1,8600,446,446,446
BEGIN DESCRIPTION:
West Dry Branch 19.0
END DESCRIPTION:
XS GIS Cut Line= 3
      1868074.98     13971675.04      1868025.00     13971775.00
      1867624.97     13971975.01
#Sta/Elev= 30
  4888.7 2001.89  4897.0 2001.79  4919.4 1999.17  4933.4 1994.34  4947.4 1986.03
  4955.7 1982.11  4964.1 1974.64  4978.1 1964.55  4986.5 1957.48  4992.1 1944.57
  4992.2 1936.16  4992.7 1935.66  5003.2 1936.16  5014.4 1938.10  5022.8 1937.40
  5031.2 1938.16  5053.6 1937.57  5067.5 1938.11  5075.9 1939.30  5081.5 1941.12
  5120.6 1941.13  5148.6 1943.35  5193.3 1944.79  5349.8 1960.99  5366.6 1963.90
  5402.9 1966.35  5433.7 1971.26  5439.3 1971.39  5444.9 1973.69  5447.7 1973.69
#Mann=3,-1,0
  4888.7    0.07       0  4992.2    0.05       0  5003.2    0.07       0
Bank Sta=4992.2,5003.2
Exp/Cntr=0.3,0.1

Type RM Length L Ch R = 1,8154,466,466,466
BEGIN DESCRIPTION:
West Dry Branch 18.0
END DESCRIPTION:
XS GIS Cut Line= 3
      1867874.98     13971375.01      1867675.00     13971525.00
      1867374.99     13971675.01
#Sta/Elev= 30
  4743.7 1997.38  4786.4 1988.97  4801.0 1982.64  4836.4 1972.62  4851.0 1965.36
  4888.3 1953.78  4901.0 1948.51  4930.1 1939.36  4936.4 1939.16  4957.2 1934.36
  4980.1 1932.04  4986.4 1930.17  4996.6 1930.17  4997.1 1929.67  5007.6 1930.17
  5030.0 1932.84  5046.8 1933.01  5052.4 1934.71  5069.1 1933.84  5074.7 1935.88
  5097.1 1933.39  5105.5 1934.69  5113.9 1938.56  5136.2 1952.42  5203.3 1961.51
  5262.0 1967.59  5276.0 1970.05  5306.7 1978.75  5317.3 1979.85  5329.1 1980.32
#Mann=5,-1,0
  4743.7     0.1       0  4888.3    0.07       0  4996.6    0.05       0
  5007.6    0.07       0  5317.3     0.1       0
Bank Sta=4996.6,5007.6
Exp/Cntr=0.3,0.1

Type RM Length L Ch R = 1,7688,453,453,453
BEGIN DESCRIPTION:
West Dry Branch 17.0
END DESCRIPTION:
XS GIS Cut Line= 3
      1867525.01     13970974.99      1867325.00     13971275.00
      1867274.99     13971375.02
#Sta/Elev= 30
  4639.4 1981.56  4668.0 1978.49  4675.5 1976.34  4683.0 1973.00  4698.0 1969.45
  4725.0 1958.82  4797.2 1936.73  4812.2 1934.82  4831.8 1934.02  4837.5 1934.00
  4884.3 1932.70  4914.3 1933.00  4935.4 1931.03  4941.4 1928.31  4947.5 1928.01
  4950.4 1927.86  4956.4 1925.09  4986.9 1921.24  4987.4 1920.74  4998.0 1921.24
  5000.0 1923.60  5002.8 1923.60  5008.4 1931.02  5013.9 1936.59  5030.7 1941.33
  5036.3 1944.36  5059.1 1950.20  5089.4 1955.22  5109.0 1959.94  5111.8 1959.94
#Mann=7,-1,0
  4639.4     0.1       0  4831.8   0.035       0  4837.5    0.07       0
  4947.5   0.035       0  4986.9   0.035       0  4998.0   0.035       0
  5059.1    0.07       0
Bank Sta=4986.9,4998
Exp/Cntr=0.3,0.1

Type RM Length L Ch R = 1,7235,417,417,417
BEGIN DESCRIPTION:
West Dry Branch 16.0
END DESCRIPTION:
XS GIS Cut Line= 3
      1867274.97     13970775.03      1867175.00     13970875.00
      1866925.03     13971124.97
#Sta/Elev= 30
  4863.7 1973.37  4867.2 1973.37  4877.8 1969.58  4906.1 1961.85  4920.2 1957.36
  4932.4 1952.75  4948.5 1944.71  4962.7 1936.35  4976.8 1924.68  4985.3 1919.78
  4985.8 1919.28  4996.0 1919.28  4996.5 1919.78  5019.2 1920.25  5047.5 1924.56
  5061.7 1925.55  5075.8 1927.37  5089.9 1927.15  5118.2 1932.25  5160.6 1936.26
  5174.8 1938.69  5218.5 1949.72  5220.6 1950.27  5245.5 1957.34  5273.8 1962.12
  5287.9 1965.56  5302.1 1967.78  5330.4 1974.71  5344.5 1977.44  5358.6 1978.35
#Mann=6,-1,0
  4863.7     0.1       0  4932.4    0.07       0  4985.3    0.05       0
  4996.5    0.07       0  5218.5   0.035       0  5220.6    0.07       0
Bank Sta=4985.3,4996.5
Exp/Cntr=0.3,0.1

Type RM Length L Ch R = 1,6818,477,477,477
BEGIN DESCRIPTION:
West Dry Branch 15.0
END DESCRIPTION:
XS GIS Cut Line= 3
      1866975.02     13970524.98      1866875.00     13970625.00
      1866774.98     13970825.04
#Sta/Elev= 30
  4863.3 1959.67  4866.9 1959.67  4877.5 1956.82  4891.6 1953.79  4919.9 1943.92
  4934.0 1937.88  4948.2 1926.49  4962.3 1916.07  4976.5 1914.65  4985.0 1914.57
  4985.5 1914.07  4995.7 1914.07  4996.2 1914.57  5001.2 1916.33  5007.5 1916.33
  5013.1 1920.14  5027.1 1922.76  5041.1 1923.70  5057.9 1923.28  5063.4 1922.56
  5071.8 1922.64  5116.5 1929.61  5130.5 1932.46  5161.3 1941.20  5169.7 1942.91
  5192.0 1948.61  5214.4 1952.80  5220.0 1953.21  5225.6 1954.53  5228.4 1954.53
#Mann=3,-1,0
  4863.3    0.07       0  4985.0    0.05       0  4996.2    0.07       0
Bank Sta=4985,4996.2
Exp/Cntr=0.3,0.1

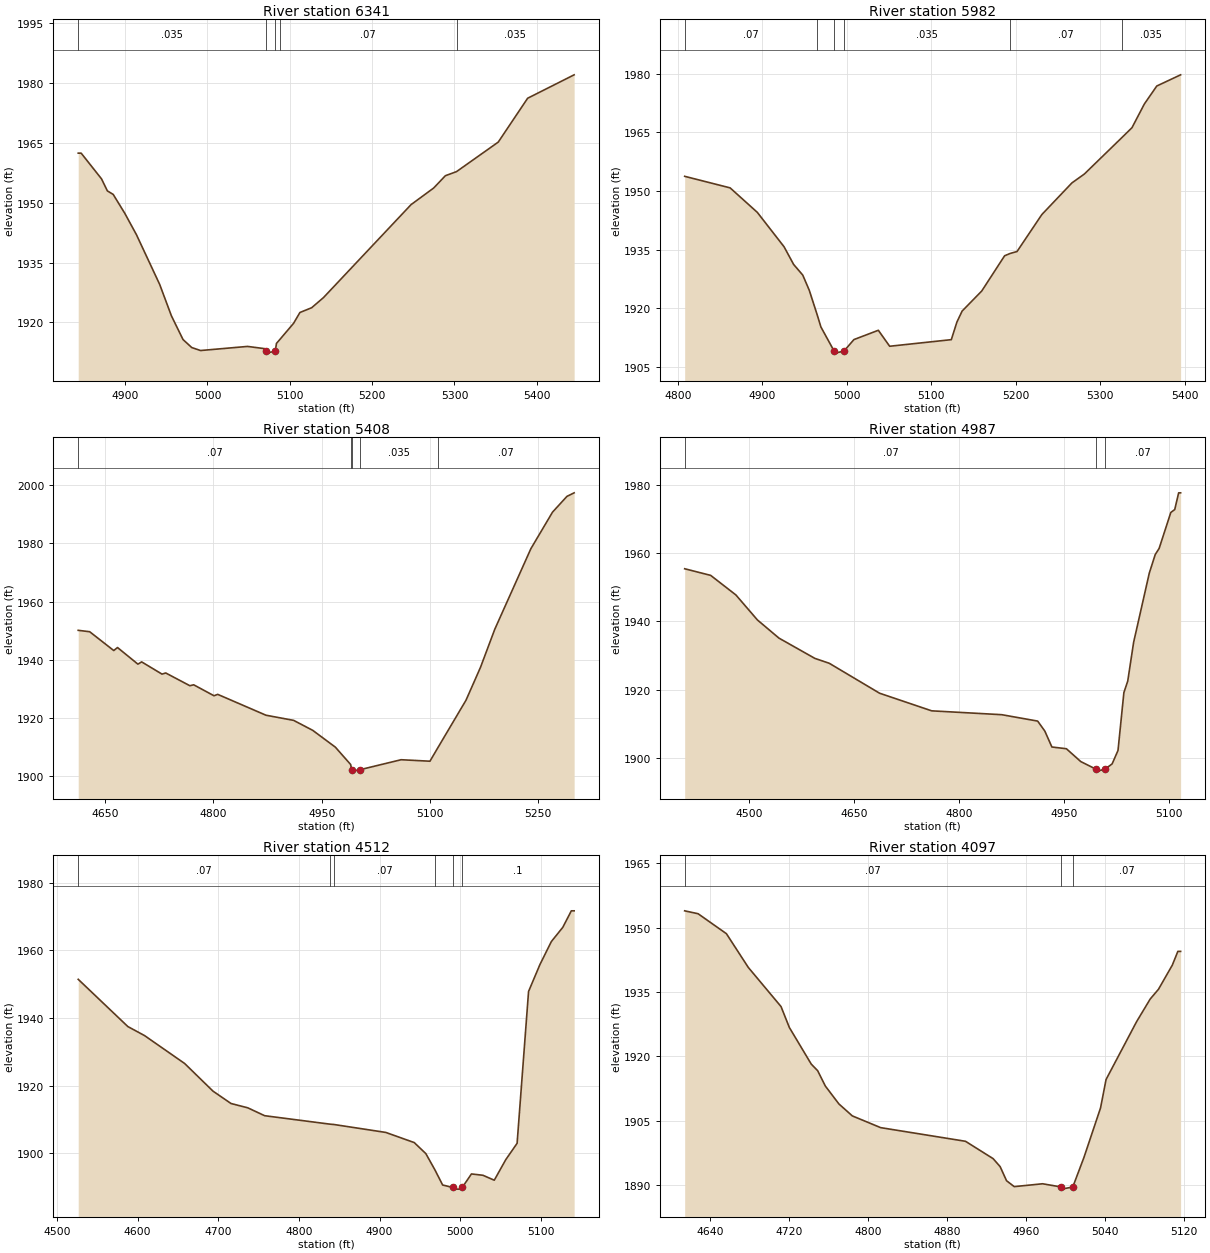
Type RM Length L Ch R = 1,6341,359,359,359
BEGIN DESCRIPTION:
West Dry Branch 14.0
END DESCRIPTION:
XS GIS Cut Line= 3
      1866625.03     13970224.97      1866525.00     13970325.00
      1866225.03     13970674.97
#Sta/Elev= 30
  4843.0 1962.40  4846.6 1962.40  4871.3 1955.96  4878.4 1952.95  4885.5 1952.06
  4899.6 1947.32  4913.8 1941.94  4942.0 1929.49  4956.2 1921.64  4970.3 1915.70
  4980.9 1913.69  4991.6 1912.94  5048.7 1913.97  5069.5 1913.41  5071.0 1912.79
  5071.5 1912.29  5082.4 1912.79  5083.8 1914.73  5087.6 1915.63  5104.6 1919.76
  5112.3 1922.47  5126.6 1923.67  5140.9 1926.20  5247.3 1949.50  5274.8 1953.67
  5289.0 1956.75  5302.5 1957.77  5353.2 1965.17  5388.9 1976.16  5445.4 1982.03
#Mann=5,-1,0
  4843.0   0.035       0  5071.0   0.035       0  5082.4   0.035       0
  5087.6    0.07       0  5302.5   0.035       0
Bank Sta=5071,5082.4
Exp/Cntr=0.3,0.1

Type RM Length L Ch R = 1,5982,574,574,574
BEGIN DESCRIPTION:
West Dry Branch 13.0
END DESCRIPTION:
XS GIS Cut Line= 3
      1866325.00     13969975.00      1866250.89     13970162.74
      1866025.02     13970474.97
#Sta/Elev= 30
  4808.0 1953.76  4861.8 1950.80  4894.0 1944.53  4925.7 1935.71  4937.0 1931.19
  4947.8 1928.47  4955.5 1924.59  4965.0 1918.23  4969.3 1915.18  4985.0 1908.98
  4985.5 1908.48  4996.5 1908.98  5008.4 1911.95  5037.3 1914.33  5050.7 1910.24
  5123.7 1911.93  5130.3 1916.42  5136.5 1919.25  5159.7 1924.38  5186.8 1933.41
  5193.3 1934.00  5201.5 1934.50  5230.9 1943.97  5266.5 1952.07  5281.2 1954.34
  5325.9 1963.73  5337.6 1966.21  5352.3 1972.29  5367.0 1976.89  5395.2 1979.75
#Mann=6,-1,0
  4808.0    0.07       0  4965.0   0.035       0  4985.0   0.035       0
  4996.5   0.035       0  5193.3    0.07       0  5325.9   0.035       0
Bank Sta=4985,4996.5
Exp/Cntr=0.3,0.1

Type RM Length L Ch R = 1,5408,421,421,421
BEGIN DESCRIPTION:
West Dry Branch 12.0
END DESCRIPTION:
XS GIS Cut Line= 3
      1866297.24     13969716.11      1865925.00     13969825.00
      1865625.04     13969825.00
#Sta/Elev= 30
  4612.4 1950.12  4628.3 1949.64  4661.7 1943.19  4666.9 1944.22  4695.2 1938.52
  4700.4 1939.29  4728.6 1935.10  4733.8 1935.49  4767.3 1931.11  4772.5 1931.44
  4800.7 1927.68  4805.9 1928.15  4872.8 1921.00  4911.2 1919.23  4937.7 1915.80
  4969.0 1910.05  4990.2 1904.10  4991.8 1902.32  4992.3 1901.82  5003.4 1902.32
  5060.2 1905.73  5100.2 1905.22  5110.9 1909.73  5150.2 1926.14  5170.2 1937.36
  5190.2 1950.53  5240.2 1978.13  5270.2 1990.66  5290.2 1996.07  5300.2 1997.29
#Mann=5,-1,0
  4612.4    0.07       0  4990.2   0.035       0  4991.8   0.035       0
  5003.4   0.035       0  5110.9    0.07       0
Bank Sta=4991.8,5003.4
Exp/Cntr=0.3,0.1

Type RM Length L Ch R = 1,4987,475,475,475
BEGIN DESCRIPTION:
West Dry Branch 11.0
END DESCRIPTION:
XS GIS Cut Line= 3
      1866406.23     13969608.27      1865825.00     13969475.00
      1865725.01     13969425.01
#Sta/Elev= 30
  4408.5 1955.47  4445.6 1953.53  4481.6 1947.79  4512.4 1940.44  4543.1 1935.12
  4594.4 1929.17  4614.9 1927.74  4686.8 1918.95  4761.2 1913.78  4861.2 1912.65
  4912.5 1910.77  4922.7 1907.85  4932.8 1903.17  4953.5 1902.66  4974.0 1898.90
  4996.4 1896.59  4996.9 1896.09  5008.1 1896.59  5018.8 1898.21  5027.2 1902.15
  5035.6 1919.14  5041.1 1922.51  5049.5 1933.88  5071.9 1954.21  5080.3 1959.61
  5085.9 1961.43  5102.6 1971.99  5108.2 1972.84  5113.8 1977.75  5116.6 1977.75
#Mann=3,-1,0
  4408.5    0.07       0  4996.4    0.05       0  5008.1    0.07       0
Bank Sta=4996.4,5008.1
Exp/Cntr=0.3,0.1

Type RM Length L Ch R = 1,4512,415,415,415
BEGIN DESCRIPTION:
West Dry Branch 10.0
END DESCRIPTION:
XS GIS Cut Line= 3
      1866443.22     13969422.37      1866075.00     13969125.00
      1865975.02     13969025.02
#Sta/Elev= 30
  4526.5 1951.42  4588.0 1937.45  4608.8 1934.76  4658.4 1926.52  4693.6 1918.33
  4715.9 1914.68  4736.7 1913.40  4757.6 1911.07  4838.6 1908.57  4843.7 1908.46
  4907.8 1906.12  4943.0 1903.12  4957.4 1899.85  4968.8 1894.97  4978.2 1890.57
  4990.7 1889.85  4991.2 1889.35  5002.0 1889.35  5002.5 1889.85  5013.9 1893.84
  5028.1 1893.45  5042.2 1891.99  5056.4 1898.05  5070.5 1902.91  5084.7 1947.83
  5098.8 1955.79  5112.9 1962.57  5127.1 1966.79  5137.7 1971.68  5141.2 1971.68
#Mann=6,-1,0
  4526.5    0.07       0  4838.6   0.035       0  4843.7    0.07       0
  4968.8   0.035       0  4990.7    0.05       0  5002.5     0.1       0
Bank Sta=4990.7,5002.5
Exp/Cntr=0.3,0.1

Type RM Length L Ch R = 1,4097,415,415,415
BEGIN DESCRIPTION:
West Dry Branch 9.0
END DESCRIPTION:
XS GIS Cut Line= 3
      1866674.97     13969124.97      1866375.00     13968875.00
      1866274.98     13968824.99
#Sta/Elev= 30
  4614.2 1953.92  4627.8 1953.24  4656.5 1948.58  4678.6 1940.73  4711.8 1931.59
  4720.2 1926.72  4742.4 1918.17  4748.9 1916.63  4756.7 1913.04  4770.4 1908.88
  4784.0 1906.09  4812.7 1903.35  4898.6 1900.17  4926.6 1896.12  4933.7 1894.26
  4940.2 1890.97  4948.0 1889.59  4976.7 1890.26  4995.5 1889.51  4996.0 1889.01
  5007.3 1889.51  5018.6 1896.41  5035.4 1907.95  5041.0 1914.58  5071.8 1928.02
  5085.7 1933.35  5094.1 1935.63  5108.1 1941.26  5113.7 1944.46  5116.5 1944.46
#Mann=3,-1,0
  4614.2    0.07       0  4995.5    0.05       0  5007.3    0.07       0
Bank Sta=4995.5,5007.3
Exp/Cntr=0.3,0.1

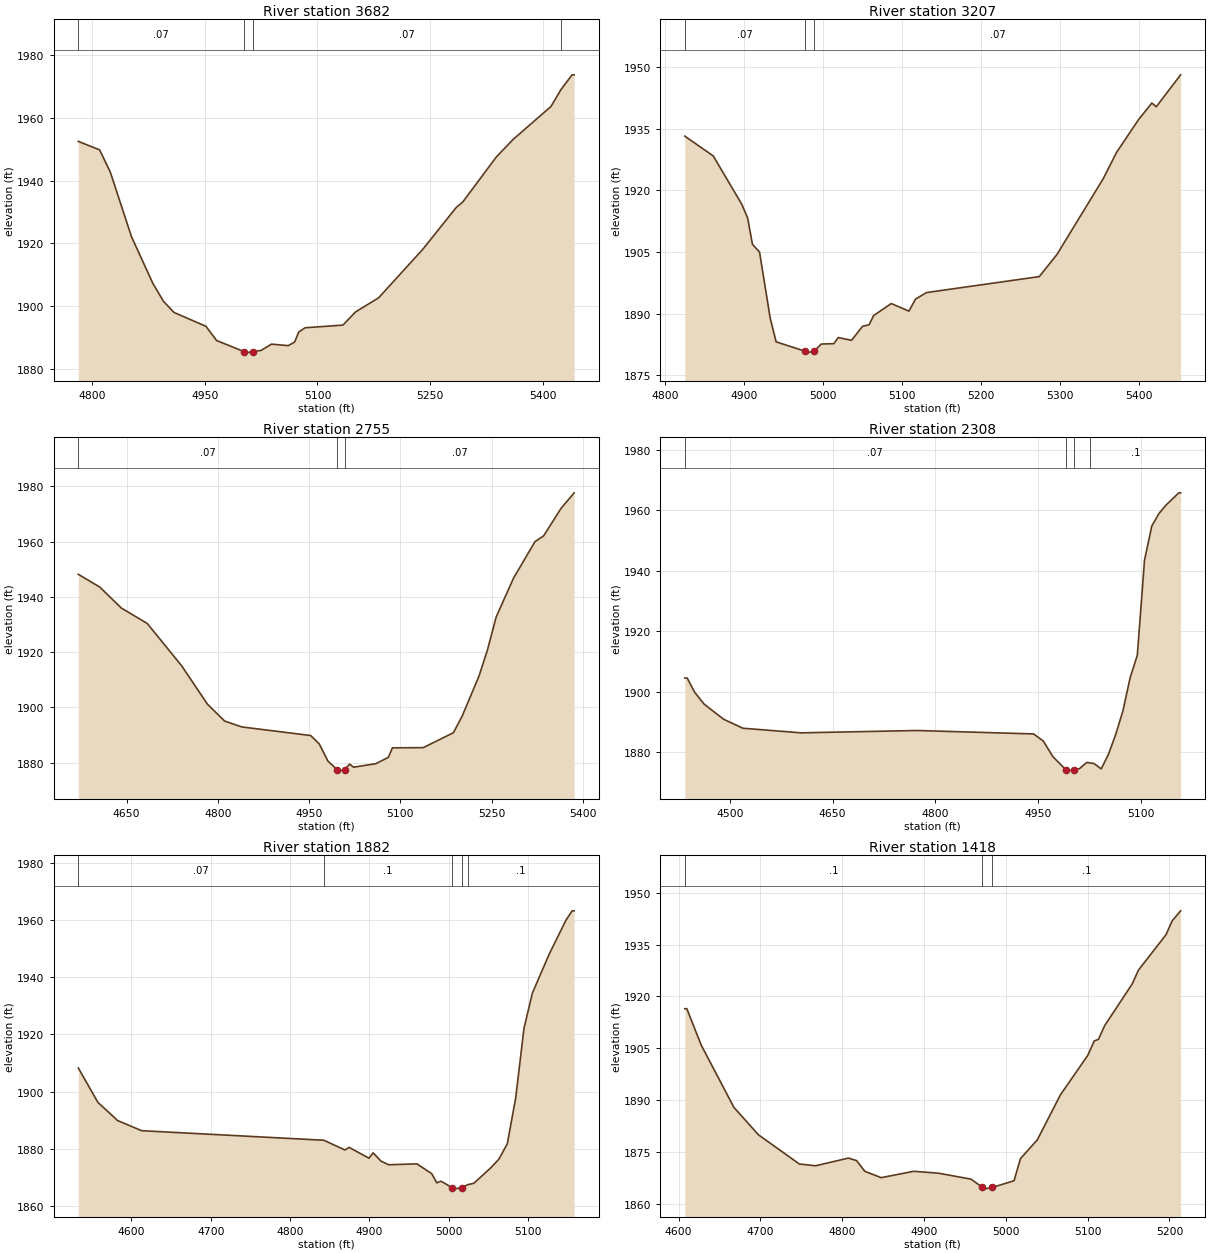
Type RM Length L Ch R = 1,3682,475,475,475
BEGIN DESCRIPTION:
West Dry Branch 8.0
END DESCRIPTION:
XS GIS Cut Line= 3
      1866875.02     13968875.02      1866725.00     13968725.00
      1866324.97     13968524.99
#Sta/Elev= 30
  4782.0 1952.50  4810.3 1949.79  4824.5 1942.72  4852.7 1922.08  4881.0 1907.24
  4895.2 1901.47  4909.3 1897.90  4951.7 1893.48  4965.9 1888.94  5002.2 1885.42
  5002.7 1884.92  5014.1 1885.42  5024.9 1885.77  5038.9 1887.79  5061.2 1887.31
  5069.6 1888.45  5075.2 1891.68  5083.6 1893.01  5133.9 1893.87  5150.7 1898.07
  5181.4 1902.58  5240.1 1918.06  5284.8 1931.47  5293.2 1933.13  5338.0 1947.56
  5360.3 1953.14  5410.6 1963.64  5423.7 1968.98  5438.6 1973.74  5441.4 1973.74
#Mann=4,-1,0
  4782.0    0.07       0  5002.2    0.05       0  5014.1    0.07       0
  5423.7   0.035       0
Bank Sta=5002.2,5014.1
Exp/Cntr=0.3,0.1

Type RM Length L Ch R = 1,3207,452,452,452
BEGIN DESCRIPTION:
West Dry Branch 7.0
END DESCRIPTION:
XS GIS Cut Line= 3
      1867074.98     13968574.97      1866975.00     13968425.00
      1866774.98     13968024.96
#Sta/Elev= 30
  4825.0 1933.16  4861.0 1928.35  4897.1 1916.61  4904.6 1913.23  4910.6 1906.87
  4919.6 1904.98  4933.1 1888.90  4940.6 1883.16  4976.7 1880.92  4977.2 1880.42
  4988.7 1880.92  4997.7 1882.63  5013.6 1882.72  5019.2 1884.21  5036.0 1883.53
  5050.0 1886.94  5058.3 1887.31  5063.9 1889.53  5086.3 1892.47  5108.7 1890.63
  5117.0 1893.55  5131.0 1895.14  5273.6 1899.02  5295.9 1904.37  5354.6 1922.83
  5371.4 1929.20  5399.3 1937.18  5416.1 1941.21  5421.7 1940.31  5452.5 1948.06
#Mann=3,-1,0
  4825.0    0.07       0  4976.7    0.05       0  4988.7    0.07       0
Bank Sta=4976.7,4988.7
Exp/Cntr=0.3,0.1

Type RM Length L Ch R = 1,2755,447,447,447
BEGIN DESCRIPTION:
West Dry Branch 6.0
END DESCRIPTION:
XS GIS Cut Line= 3
      1867525.01     13968375.01      1867225.00     13968075.00
      1866975.00     13967775.00
#Sta/Elev= 30
  4570.7 1948.14  4606.1 1943.49  4641.4 1935.92  4683.9 1930.36  4740.4 1915.06
  4782.8 1901.16  4811.1 1895.03  4839.4 1892.90  4952.6 1889.79  4966.7 1886.74
  4980.8 1880.56  4996.1 1877.41  4996.6 1876.91  5008.2 1877.41  5016.5 1879.45
  5023.0 1878.34  5059.4 1879.58  5080.2 1881.90  5086.8 1885.34  5137.5 1885.41
  5187.0 1890.80  5201.3 1896.74  5229.3 1911.41  5243.0 1920.76  5257.3 1932.66
  5285.9 1946.76  5321.1 1959.94  5335.4 1962.07  5364.0 1972.01  5385.5 1977.62
#Mann=3,-1,0
  4570.7    0.07       0  4996.1    0.05       0  5008.2    0.07       0
Bank Sta=4996.1,5008.2
Exp/Cntr=0.3,0.1

Type RM Length L Ch R = 1,2308,426,426,426
BEGIN DESCRIPTION:
West Dry Branch 5.0
END DESCRIPTION:
XS GIS Cut Line= 3
      1867774.97     13968074.97      1867375.00     13967675.00
      1867325.02     13967525.05
#Sta/Elev= 30
  4434.3 1904.52  4437.8 1904.52  4448.4 1899.90  4462.5 1895.89  4490.8 1890.92
  4519.1 1887.92  4604.0 1886.40  4773.7 1887.17  4943.4 1886.04  4957.5 1883.70
  4971.7 1878.49  4990.4 1874.24  4990.9 1873.74  5002.5 1874.24  5010.5 1874.58
  5021.0 1876.61  5025.8 1876.45  5031.6 1876.25  5042.1 1874.49  5052.6 1879.25
  5063.2 1885.85  5073.7 1893.58  5084.3 1904.59  5094.8 1912.08  5105.3 1943.46
  5115.9 1954.76  5126.4 1958.92  5137.0 1961.77  5155.4 1965.75  5158.0 1965.75
#Mann=4,-1,0
  4434.3    0.07       0  4990.4    0.05       0  5002.5    0.07       0
  5025.8     0.1       0
Bank Sta=4990.4,5002.5
Exp/Cntr=0.3,0.1

Type RM Length L Ch R = 1,1882,464,464,464
BEGIN DESCRIPTION:
West Dry Branch 4.0
END DESCRIPTION:
XS GIS Cut Line= 3
      1867888.91     13968062.28      1867725.00     13967625.00
      1867675.00     13967475.00
#Sta/Elev= 30
  4533.1 1908.28  4557.7 1896.29  4582.6 1889.91  4612.9 1886.36  4842.6 1883.02
  4869.2 1879.62  4874.6 1880.51  4899.5 1876.75  4904.8 1878.62  4914.7 1875.71
  4924.4 1874.45  4960.0 1874.76  4978.7 1871.32  4985.0 1868.13  4990.3 1868.71
  5004.5 1866.43  5005.0 1865.93  5016.7 1866.43  5024.0 1867.49  5031.7 1867.97
  5052.8 1873.30  5063.3 1876.39  5073.9 1881.78  5084.4 1897.65  5095.0 1922.23
  5105.5 1934.44  5126.6 1947.99  5147.7 1959.87  5155.6 1963.22  5158.2 1963.22
#Mann=5,-1,0
  4533.1    0.07       0  4842.6     0.1       0  5004.5    0.05       0
  5016.7     0.1       0  5024.0     0.1       0
Bank Sta=5004.5,5016.7
Exp/Cntr=0.3,0.1

Type RM Length L Ch R = 1,1418,447,447,447
BEGIN DESCRIPTION:
West Dry Branch 3.0
END DESCRIPTION:
XS GIS Cut Line= 3
      1868175.00     13967974.96      1868175.00     13967575.00
      1868125.00     13967375.02
#Sta/Elev= 30
  4607.6 1916.45  4610.1 1916.45  4627.6 1905.94  4667.6 1887.88  4697.6 1879.93
  4747.6 1871.46  4767.6 1870.95  4807.6 1873.17  4817.6 1872.45  4827.6 1869.36
  4847.6 1867.50  4887.6 1869.35  4917.6 1868.80  4957.6 1867.07  4971.5 1864.68
  4972.0 1864.18  4983.7 1864.68  5010.1 1866.61  5017.9 1873.01  5038.5 1878.45
  5066.8 1891.51  5100.3 1902.97  5108.1 1907.11  5113.2 1907.57  5120.9 1911.57
  5154.4 1923.58  5162.2 1927.65  5195.7 1937.85  5203.4 1941.91  5213.7 1944.81
#Mann=3,-1,0
  4607.6     0.1       0  4971.5    0.05       0  4983.7     0.1       0
Bank Sta=4971.5,4983.7
Exp/Cntr=0.3,0.1

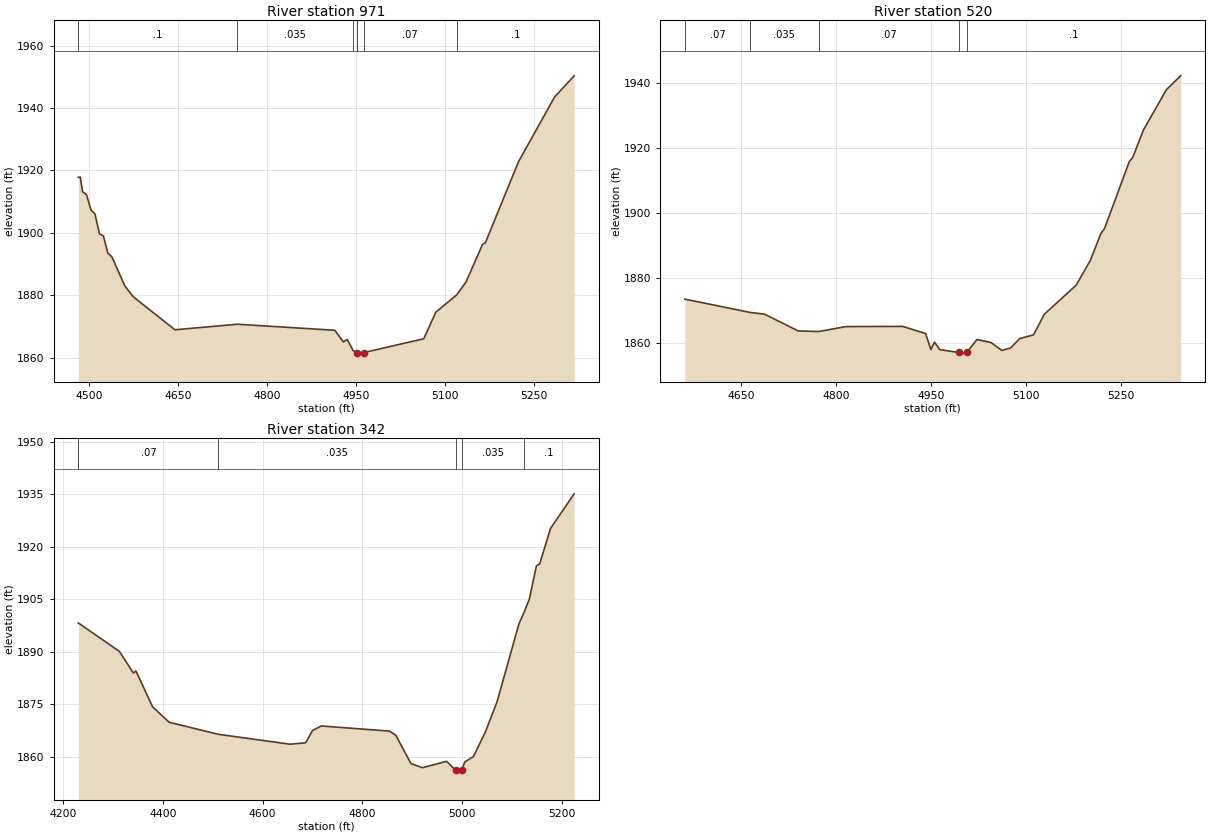
Type RM Length L Ch R = 1,971,451,451,451
BEGIN DESCRIPTION:
West Dry Branch 2.0
END DESCRIPTION:
XS GIS Cut Line= 3
      1868225.00     13967975.00      1868575.00     13967575.00
      1868525.01     13967275.05
#Sta/Elev= 30
  4481.9 1917.84  4485.2 1917.84  4489.0 1913.18  4495.7 1912.22  4503.3 1907.31
  4509.9 1906.10  4517.5 1899.68  4524.1 1899.02  4531.7 1893.50  4538.4 1892.32
  4560.2 1882.99  4574.4 1879.51  4644.7 1868.90  4749.9 1870.68  4914.2 1868.74
  4928.5 1865.00  4935.1 1865.82  4944.8 1862.26  4950.8 1861.59  4951.3 1861.09
  4963.0 1861.59  5064.1 1866.03  5084.4 1874.56  5119.3 1880.05  5135.1 1884.16
  5162.9 1896.20  5168.0 1896.88  5223.8 1922.84  5284.6 1943.59  5317.5 1950.36
#Mann=6,-1,0
  4481.9     0.1       0  4749.9   0.035       0  4944.8    0.07       0
  4950.8    0.05       0  4963.0    0.07       0  5119.3     0.1       0
Bank Sta=4950.8,4963
Exp/Cntr=0.3,0.1

Type RM Length L Ch R = 1,520,178,178,178
BEGIN DESCRIPTION:
West Dry Branch 1.0
END DESCRIPTION:
XS GIS Cut Line= 3
      1868775.00     13967925.00      1868975.00     13967525.00
      1868825.01     13967225.02
#Sta/Elev= 30
  4561.2 1873.54  4664.3 1869.45  4687.0 1868.92  4740.1 1863.79  4772.5 1863.59
  4815.6 1865.11  4905.0 1865.17  4941.3 1862.97  4949.7 1858.06  4955.3 1860.33
  4963.7 1858.05  4993.9 1857.15  4994.4 1856.65  5006.1 1857.15  5022.4 1861.13
  5044.7 1860.21  5061.5 1857.78  5075.5 1858.54  5089.5 1861.39  5111.8 1862.59
  5128.6 1868.88  5178.9 1877.82  5201.3 1885.42  5218.0 1893.73  5223.6 1895.17
  5262.8 1915.76  5268.4 1917.12  5285.1 1925.48  5321.5 1937.88  5343.8 1942.11
#Mann=5,-1,0
  4561.2    0.07       0  4664.3   0.035       0  4772.5    0.07       0
  4993.9    0.05       0  5006.1     0.1       0
Bank Sta=4993.9,5006.1
Exp/Cntr=0.3,0.1

Type RM Length L Ch R = 1,342,0,0,0
BEGIN DESCRIPTION:
West Dry Branch 0.0
END DESCRIPTION:
XS GIS Cut Line= 4
      1868957.75     13968132.32      1869120.94     13967578.28
      1869009.62     13967302.43      1868929.91     13967213.19
#Sta/Elev= 30
  4230.4 1898.18  4312.7 1890.06  4340.8 1883.88  4346.0 1884.45  4379.4 1874.20
  4412.7 1869.79  4511.5 1866.35  4655.0 1863.52  4686.3 1863.92  4700.2 1867.42
  4717.6 1868.73  4854.6 1867.27  4867.4 1866.07  4897.8 1857.97  4921.1 1856.81
  4969.4 1858.63  4987.3 1856.04  4987.8 1855.54  4999.6 1856.04  5005.6 1858.46
  5023.0 1859.96  5047.2 1867.10  5070.3 1875.59  5114.3 1897.91  5124.3 1901.11
  5135.2 1904.97  5149.4 1914.53  5156.1 1915.09  5177.8 1925.23  5225.1 1935.09
#Mann=5,-1,0
  4230.4    0.07       0  4511.5   0.035       0  4987.3   0.035       0
  4999.6   0.035       0  5124.3     0.1       0
Bank Sta=4987.3,4999.6
Exp/Cntr=0.3,0.1

Chan Stop Cuts=-1