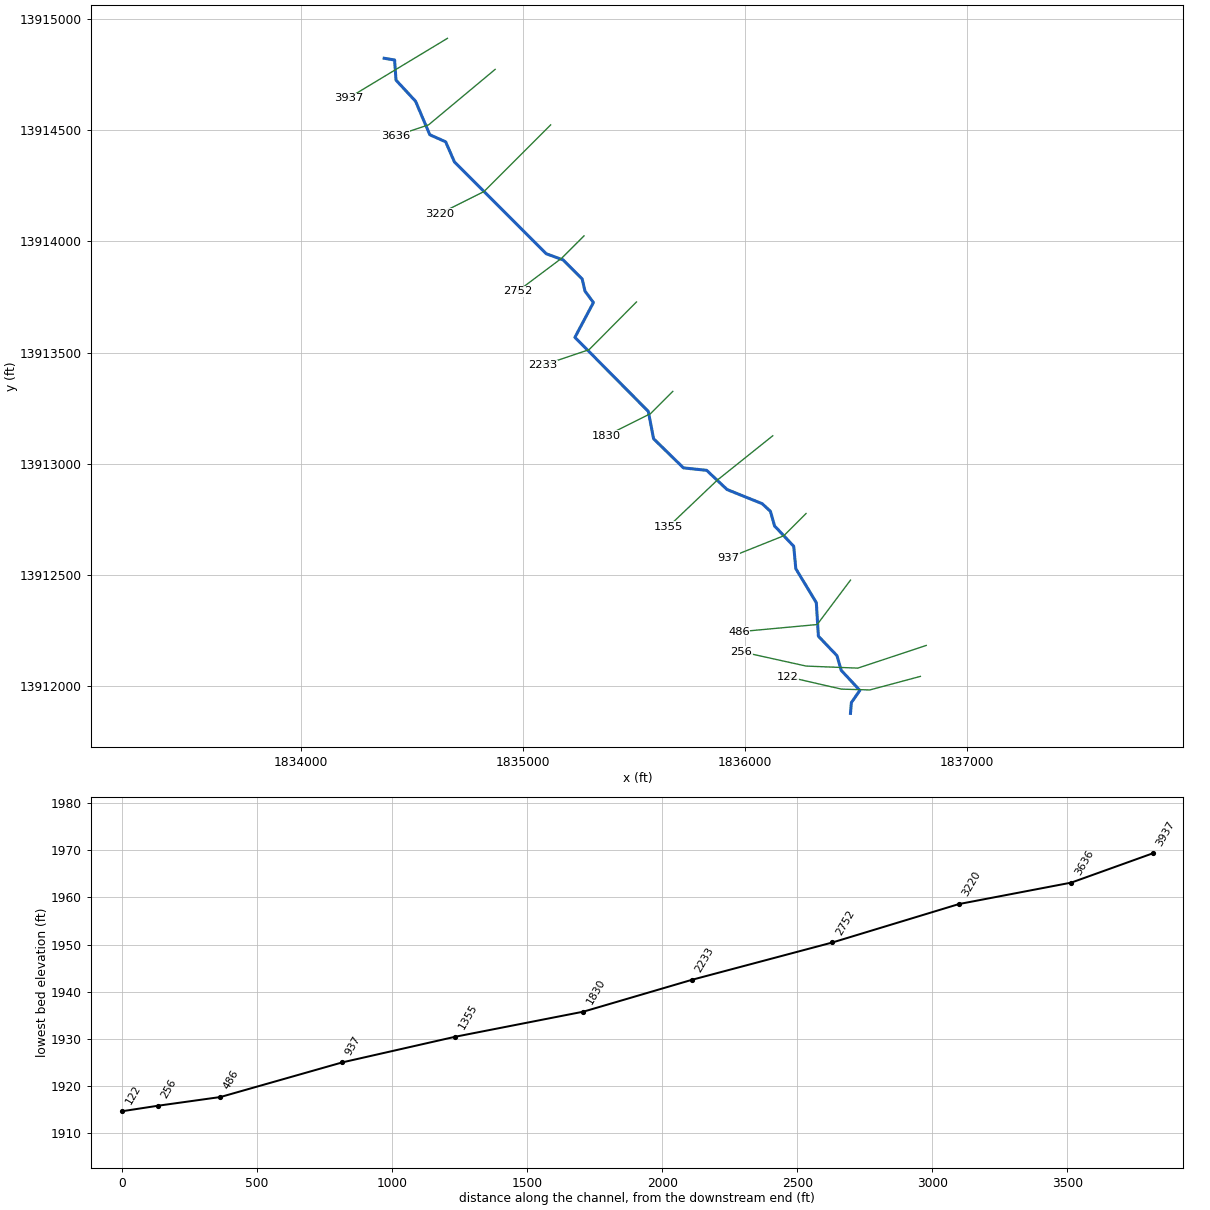
--- White Oak Creek.prj (project) ---

Proj Title=White Oak Creek Base Level Engineering
Current Plan=p01
Default Exp/Contr=0.3,0.1
English Units
Geom File=g01
Flow File=f01
Plan File=p01
BEGIN DESCRIPTION:
White Oak Creek
END DESCRIPTION:

--- White Oak Creek.p01 (plan) ---

Plan Title=Multiple Run
Short Identifier=Multiple
Geom File=g01
Flow File=f01
Subcritical Flow
K Sum by GR= 0
Std Step Tol= 0.01
Critical Tol= 0.01
Num of Std Step Trials= 20
Max Error Tol= 0.3
Flow Tol Ratio= 0.001
Split Flow NTrial= 30
Split Flow Tol= 0.02
Split Flow Ratio= 0.02
Log Output Level= 0
Friction Slope Method= 1
Unsteady Friction Slope Method= 2
Unsteady Bridges Friction Slope Method= 1
Parabolic Critical Depth
Global Vel Dist=  1 , 1 , 1
Global Log Level= 0
CheckData=True
Encroach Param= -1, 0, 0, 0
BEGIN DESCRIPTION:
Multiple Run
END DESCRIPTION:

--- White Oak Creek.f01 (steady flow) ---

Flow Title=Multiple
Number of Profiles=7
Profile Names=10-year,25-year,50-year,1pct_min,100-year,1pct_plu,500-year
River Rch & RM= White Oak Creek,Reach-1,3937
    1421    2486    3524    2414    4817    9610    8895
River Rch & RM= White Oak Creek,Reach-1,1830
    1481    2592    3676    2518    5023   10023    9277
Boundary for River Rch & Prof#=White Oak Creek,Reach-1,1
Up Type=0
Dn Type=3
Dn Slope=0.005
Boundary for River Rch & Prof#=White Oak Creek,Reach-1,2
Up Type=0
Dn Type=3
Dn Slope=0.005
Boundary for River Rch & Prof#=White Oak Creek,Reach-1,3
Up Type=0
Dn Type=3
Dn Slope=0.005
Boundary for River Rch & Prof#=White Oak Creek,Reach-1,4
Up Type=0
Dn Type=3
Dn Slope=0.005
Boundary for River Rch & Prof#=White Oak Creek,Reach-1,5
Up Type=0
Dn Type=3
Dn Slope=0.005
Boundary for River Rch & Prof#=White Oak Creek,Reach-1,6
Up Type=0
Dn Type=3
Dn Slope=0.005
Boundary for River Rch & Prof#=White Oak Creek,Reach-1,7
Up Type=0
Dn Type=3
Dn Slope=0.005

--- White Oak Creek.g01 (geometry) ---

Geom Title=Existing Conditions

River Reach=White Oak Creek,Reach-1
Reach XY= 30
      1834375.00     13914825.00      1834422.16     13914817.24
      1834428.58     13914726.53      1834516.84     13914631.05
      1834580.62     13914480.62      1834652.02     13914448.79
      1834691.65     13914358.34      1835104.91     13913944.79
      1835181.07     13913916.85      1835266.89     13913831.07
      1835279.46     13913776.65      1835317.50     13913725.00
      1835234.11     13913568.27      1835564.56     13913234.82
      1835588.40     13913111.70      1835722.57     13912980.52
      1835827.42     13912969.46      1835918.95     13912883.16
      1836077.55     13912819.27      1836114.35     13912785.00
      1836133.19     13912718.98      1836219.46     13912627.42
      1836228.83     13912526.59      1836321.24     13912373.44
      1836330.48     13912222.56      1836414.20     13912134.67
      1836433.20     13912068.95      1836517.40     13911978.38
      1836479.02     13911923.64      1836475.00     13911875.00

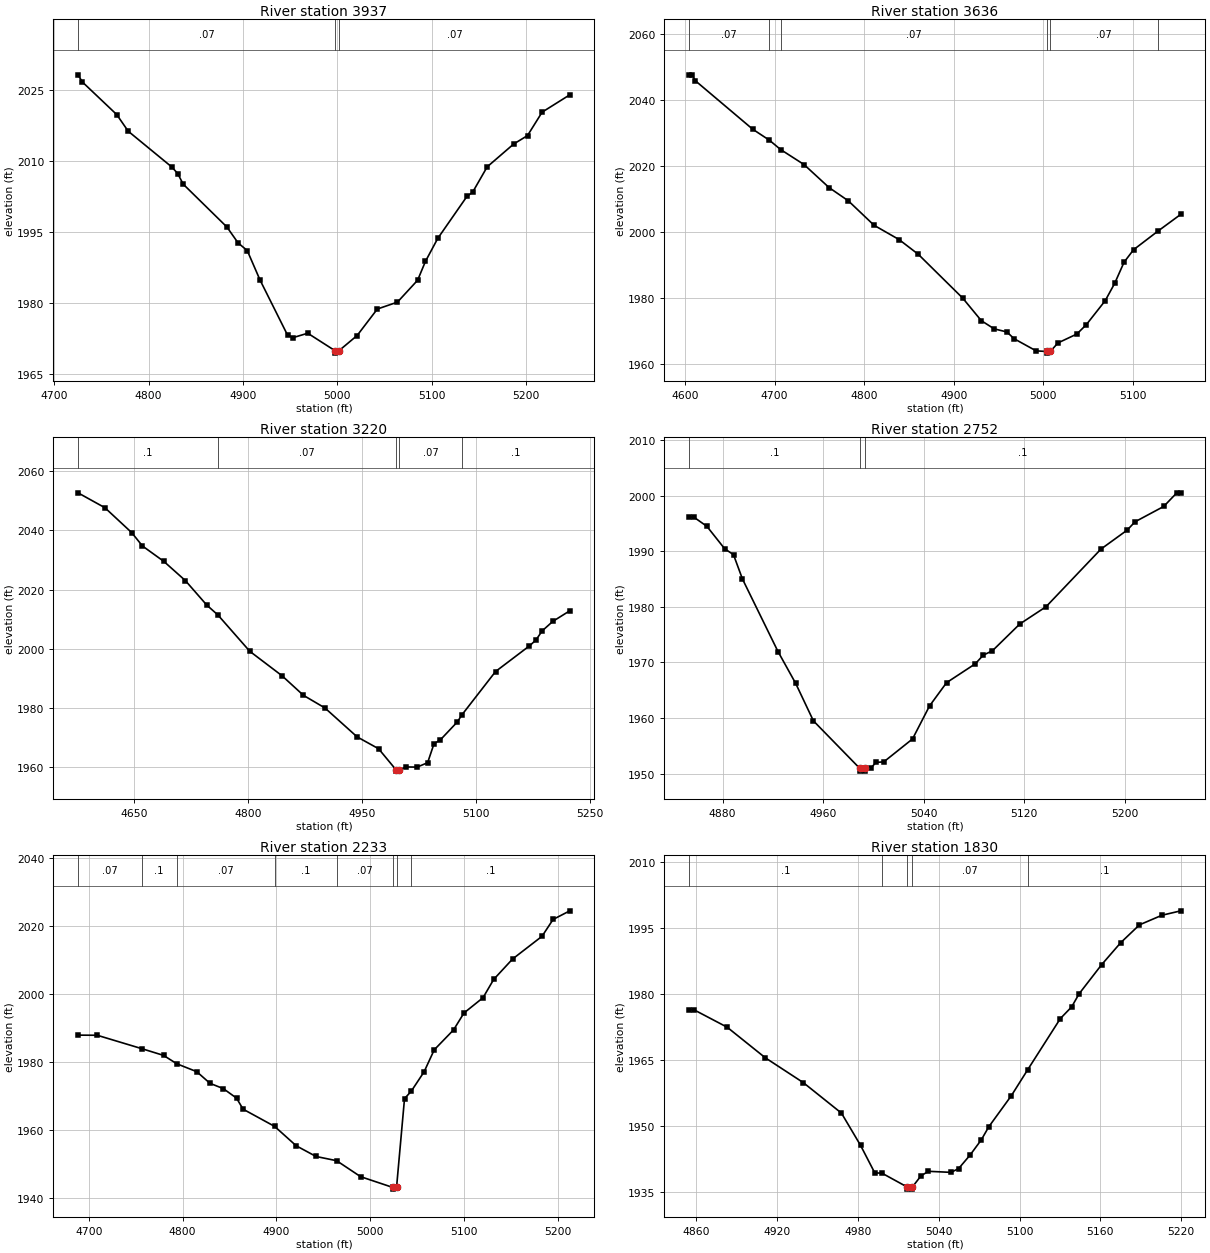
Type RM Length L Ch R = 1,3937,301,301,301
BEGIN DESCRIPTION:
White Oak Creek 9.0
END DESCRIPTION:
XS GIS Cut Line= 2
      1834660.08     13914914.73      1834214.10     13914645.39
#Sta/Elev= 30
  4725.2 2028.14  4729.8 2026.63  4766.2 2019.75  4778.4 2016.23  4824.6 2008.67
  4830.8 2007.30  4836.6 2005.06  4883.0 1995.99  4894.8 1992.64  4904.5 1991.03
  4918.1 1984.78  4947.2 1973.17  4953.1 1972.65  4968.6 1973.57  4997.6 1969.87
  4997.8 1969.37  5001.6 1969.87  5020.9 1973.09  5042.3 1978.68  5063.6 1980.14
  5085.0 1984.77  5093.3 1988.75  5106.3 1993.59  5137.4 2002.51  5143.2 2003.33
  5158.7 2008.71  5186.7 2013.52  5201.4 2015.31  5216.9 2020.26  5246.2 2023.92
#Mann=3,-1,0
  4725.2    0.07       0  4997.6    0.05       0  5001.6    0.07       0
Bank Sta=4997.6,5001.6
Exp/Cntr=0.3,0.1

Type RM Length L Ch R = 1,3636,416,416,416
BEGIN DESCRIPTION:
White Oak Creek 8.0
END DESCRIPTION:
XS GIS Cut Line= 3
      1834875.03     13914775.02      1834575.00     13914525.00
      1834424.96     13914474.99
#Sta/Elev= 30
  4604.6 2047.52  4607.9 2047.52  4611.8 2045.69  4675.6 2031.04  4694.3 2027.69
  4706.8 2024.87  4732.9 2020.32  4760.8 2013.35  4782.3 2009.33  4811.0 2001.92
  4838.9 1997.59  4860.4 1993.11  4909.9 1979.85  4930.7 1973.00  4945.0 1970.52
  4959.3 1969.57  4967.2 1967.54  4991.9 1963.84  5003.7 1963.66  5003.9 1963.16
  5007.7 1963.66  5016.2 1966.25  5037.3 1968.95  5047.8 1971.77  5068.9 1979.04
  5079.5 1984.31  5090.0 1990.74  5100.6 1994.51  5127.7 2000.13  5153.3 2005.24
#Mann=6,-1,0
  4604.6    0.07       0  4694.3     0.1       0  4706.8    0.07       0
  5003.7    0.05       0  5007.7    0.07       0  5127.7     0.1       0
Bank Sta=5003.7,5007.7
Exp/Cntr=0.3,0.1

Type RM Length L Ch R = 1,3220,468,468,468
BEGIN DESCRIPTION:
White Oak Creek 7.0
END DESCRIPTION:
XS GIS Cut Line= 3
      1835125.02     13914525.02      1834825.00     13914225.00
      1834625.00     13914125.00
#Sta/Elev= 30
  4575.7 2052.74  4611.1 2047.71  4646.4 2039.29  4660.6 2034.76  4688.9 2029.52
  4717.1 2023.06  4745.4 2014.75  4759.9 2011.45  4802.0 1999.14  4844.4 1990.88
  4872.7 1984.24  4901.0 1979.97  4943.4 1970.19  4971.7 1966.17  4994.5 1959.10
  4994.7 1958.60  4998.5 1959.10  5008.4 1960.01  5022.4 1959.96  5036.3 1961.44
  5044.7 1967.86  5053.1 1969.18  5075.5 1975.26  5081.4 1977.61  5125.8 1992.29
  5170.5 2000.98  5178.9 2002.92  5187.3 2006.06  5201.2 2009.25  5223.6 2012.84
#Mann=5,-1,0
  4575.7     0.1       0  4759.9    0.07       0  4994.5    0.05       0
  4998.5    0.07       0  5081.4     0.1       0
Bank Sta=4994.5,4998.5
Exp/Cntr=0.3,0.1

Type RM Length L Ch R = 1,2752,519,519,519
BEGIN DESCRIPTION:
White Oak Creek 6.0
END DESCRIPTION:
XS GIS Cut Line= 3
      1835275.03     13914025.03      1835175.00     13913925.00
      1834974.98     13913774.98
#Sta/Elev= 30
  4853.3 1996.19  4856.9 1996.19  4867.5 1994.50  4881.6 1990.48  4888.7 1989.39
  4895.8 1985.03  4924.1 1971.97  4938.2 1966.23  4952.3 1959.49  4989.2 1950.94
  4989.5 1950.44  4993.0 1950.44  4993.2 1950.94  4997.9 1950.94  5002.1 1952.02
  5008.3 1952.10  5031.2 1956.23  5044.8 1962.19  5058.3 1966.36  5081.2 1969.76
  5087.5 1971.31  5094.8 1972.10  5116.6 1976.92  5137.5 1980.03  5181.2 1990.40
  5202.1 1993.82  5208.3 1995.31  5231.2 1998.08  5241.6 2000.53  5244.8 2000.53
#Mann=3,-1,0
  4853.3     0.1       0  4989.2    0.05       0  4993.2     0.1       0
Bank Sta=4989.2,4993.2
Exp/Cntr=0.3,0.1

Type RM Length L Ch R = 1,2233,403,403,403
BEGIN DESCRIPTION:
White Oak Creek 5.0
END DESCRIPTION:
XS GIS Cut Line= 3
      1835511.29     13913727.69      1835298.16     13913512.93
      1835088.15     13913441.78
#Sta/Elev= 30
  4688.5 1987.90  4709.0 1987.86  4756.4 1983.92  4779.7 1981.93  4793.8 1979.46
  4815.1 1977.13  4829.2 1973.70  4843.4 1972.14  4857.5 1969.34  4864.5 1966.08
  4898.1 1961.01  4921.1 1955.30  4942.3 1952.14  4964.2 1950.90  4989.8 1946.19
  5024.1 1943.02  5024.3 1942.52  5028.1 1943.02  5036.6 1969.20  5043.7 1971.34
  5057.5 1977.11  5068.3 1983.58  5088.9 1989.45  5100.0 1994.43  5120.3 1998.93
  5131.7 2004.33  5151.8 2010.33  5183.2 2017.03  5195.0 2021.99  5212.8 2024.53
#Mann=8,-1,0
  4688.5    0.07       0  4756.4     0.1       0  4793.8    0.07       0
  4898.1     0.1       0  4964.2    0.07       0  5024.1    0.05       0
  5028.1    0.07       0  5043.7     0.1       0
Bank Sta=5024.1,5028.1
Exp/Cntr=0.3,0.1

Type RM Length L Ch R = 1,1830,475,475,475
BEGIN DESCRIPTION:
White Oak Creek 4.0
END DESCRIPTION:
XS GIS Cut Line= 3
      1835674.99     13913324.99      1835575.00     13913225.00
      1835375.01     13913125.01
#Sta/Elev= 30
  4854.7 1976.42  4858.2 1976.42  4883.0 1972.44  4911.3 1965.51  4939.5 1959.88
  4967.8 1952.97  4982.0 1945.65  4992.6 1939.38  4997.7 1939.38  5016.5 1936.23
  5016.7 1935.73  5020.2 1935.73  5020.5 1936.23  5026.9 1938.76  5032.4 1939.77
  5049.2 1939.53  5054.8 1940.40  5063.2 1943.42  5071.6 1946.90  5077.2 1949.88
  5093.9 1956.91  5106.1 1962.83  5130.3 1974.41  5138.7 1977.06  5144.2 1980.02
  5161.0 1986.65  5175.0 1991.58  5189.0 1995.65  5205.7 1997.83  5219.7 1998.83
#Mann=5,-1,0
  4854.7     0.1       0  4997.7    0.07       0  5016.5    0.05       0
  5020.5    0.07       0  5106.1     0.1       0
Bank Sta=5016.5,5020.5
Exp/Cntr=0.3,0.1

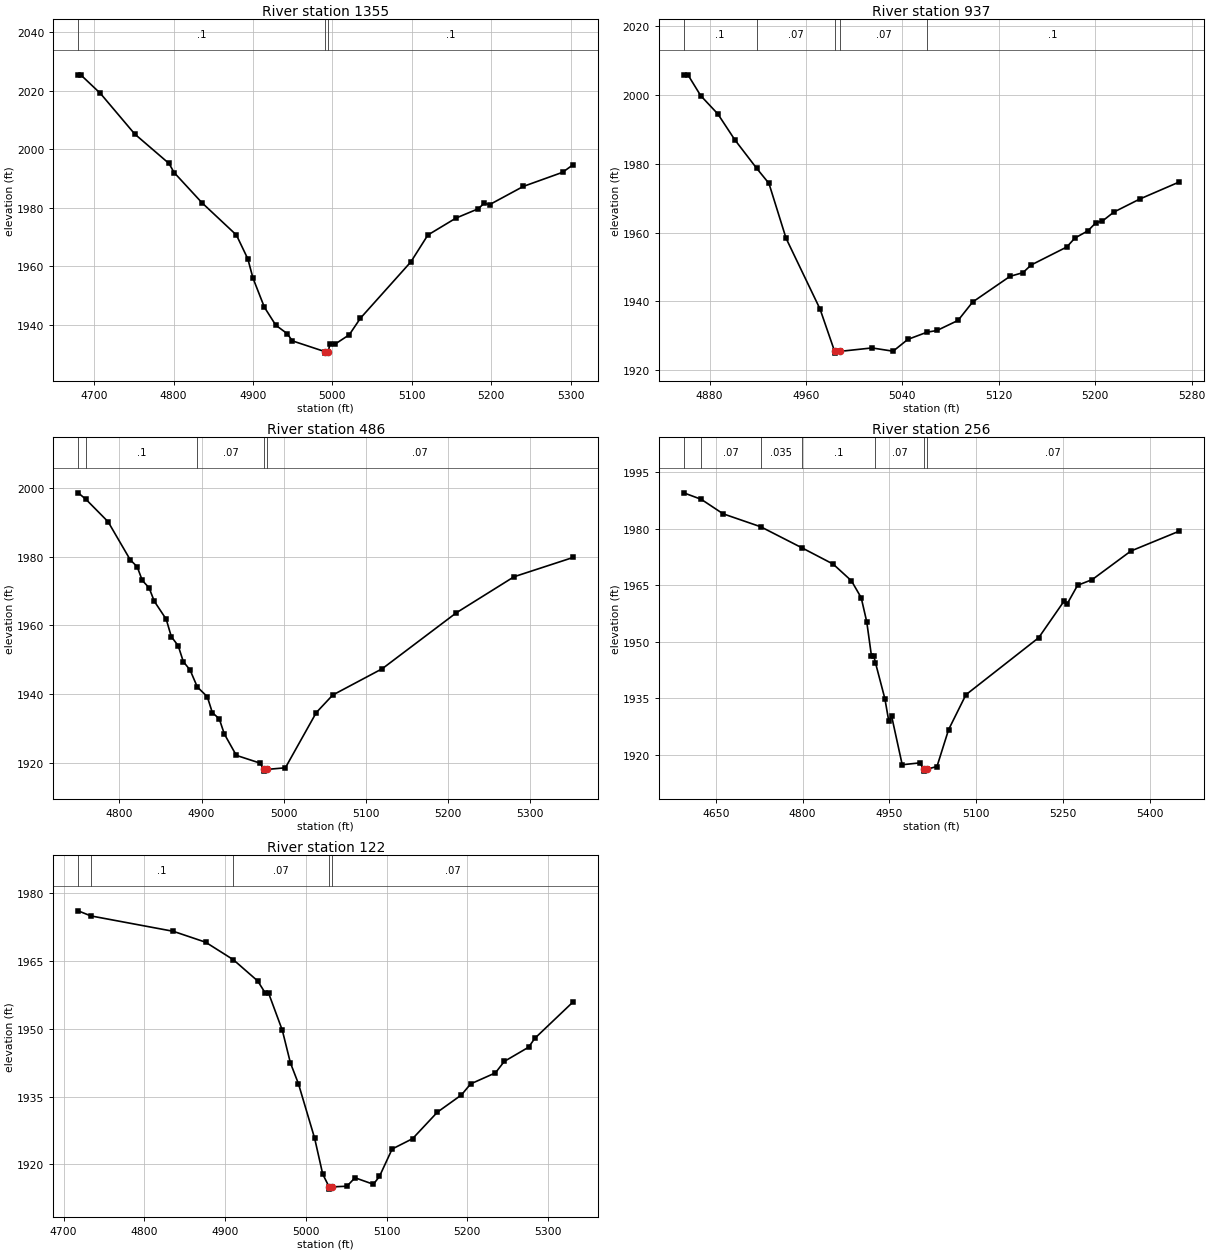
Type RM Length L Ch R = 1,1355,418,418,418
BEGIN DESCRIPTION:
White Oak Creek 3.0
END DESCRIPTION:
XS GIS Cut Line= 3
      1836124.97     13913124.98      1835875.00     13912925.00
      1835655.22     13912715.88
#Sta/Elev= 30
  4679.9 2025.44  4683.1 2025.44  4707.9 2019.09  4751.1 2005.23  4794.3 1995.16
  4800.7 1992.07  4835.9 1981.72  4879.2 1970.72  4893.6 1962.55  4900.0 1956.05
  4914.4 1946.07  4928.8 1939.92  4943.2 1937.03  4949.6 1934.58  4990.8 1930.89
  4991.0 1930.39  4994.9 1930.89  4996.8 1933.48  5003.5 1933.48  5021.3 1936.66
  5035.4 1942.33  5098.9 1961.56  5120.3 1970.73  5155.6 1976.50  5183.9 1979.71
  5191.1 1981.59  5198.0 1981.10  5240.5 1987.33  5289.9 1992.14  5303.4 1994.77
#Mann=3,-1,0
  4679.9     0.1       0  4990.8    0.05       0  4994.9     0.1       0
Bank Sta=4990.8,4994.9
Exp/Cntr=0.3,0.1

Type RM Length L Ch R = 1,937,451,451,451
BEGIN DESCRIPTION:
White Oak Creek 2.0
END DESCRIPTION:
XS GIS Cut Line= 3
      1836275.00     13912775.00      1836175.00     13912675.00
      1835924.99     13912574.99
#Sta/Elev= 30
  4858.6 2005.85  4862.1 2005.85  4872.7 1999.79  4886.9 1994.48  4901.0 1986.96
  4919.1 1978.68  4929.3 1974.29  4943.5 1958.34  4971.7 1937.75  4983.8 1925.44
  4984.1 1924.94  4988.0 1925.44  5014.8 1926.45  5032.3 1925.50  5044.5 1928.93
  5060.4 1931.02  5068.7 1931.52  5086.2 1934.46  5098.3 1939.80  5129.3 1947.27
  5140.0 1948.33  5146.8 1950.56  5176.4 1955.80  5183.1 1958.40  5193.9 1960.49
  5200.6 1962.88  5206.0 1963.36  5215.4 1965.94  5237.0 1969.75  5269.3 1974.64
#Mann=5,-1,0
  4858.6     0.1       0  4919.1    0.07       0  4983.8    0.05       0
  4988.0    0.07       0  5060.4     0.1       0
Bank Sta=4983.8,4988
Exp/Cntr=0.3,0.1

Type RM Length L Ch R = 1,486,230,230,230
BEGIN DESCRIPTION:
White Oak Creek 1.0
END DESCRIPTION:
XS GIS Cut Line= 3
      1836474.99     13912474.98      1836325.00     13912275.00
      1835973.18     13912242.44
#Sta/Elev= 30
  4749.7 1998.55  4759.2 1996.65  4786.1 1990.15  4813.2 1979.04  4821.6 1977.05
  4827.8 1973.07  4836.1 1970.92  4842.4 1967.03  4857.0 1961.76  4863.2 1956.71
  4871.6 1954.05  4877.8 1949.45  4886.1 1946.98  4894.9 1942.05  4907.0 1939.25
  4913.2 1934.60  4921.6 1932.80  4927.8 1928.39  4942.4 1922.17  4971.6 1919.89
  4975.7 1918.08  4976.0 1917.58  4979.9 1918.08  5002.2 1918.55  5039.9 1934.63
  5059.9 1939.72  5120.2 1947.37  5210.6 1963.66  5280.9 1974.14  5353.0 1979.76
#Mann=5,-1,0
  4749.7    0.07       0  4759.2     0.1       0  4894.9    0.07       0
  4975.7    0.05       0  4979.9    0.07       0
Bank Sta=4975.7,4979.9
Exp/Cntr=0.3,0.1

Type RM Length L Ch R = 1,256,134,134,134
BEGIN DESCRIPTION:
White Oak Creek 0.0
END DESCRIPTION:
XS GIS Cut Line= 4
      1836816.20     13912180.92      1836508.07     13912078.76
      1836275.69     13912087.96      1835984.10     13912152.33
#Sta/Elev= 30
  4594.6 1989.46  4624.9 1987.74  4662.7 1983.90  4727.7 1980.47  4798.5 1974.93
  4852.9 1970.58  4884.5 1966.16  4901.4 1961.68  4911.0 1955.29  4919.2 1946.18
  4923.3 1946.18  4926.1 1944.42  4942.3 1934.95  4949.0 1929.05  4954.0 1930.29
  4972.3 1917.43  5002.4 1917.92  5010.3 1916.24  5010.5 1915.74  5014.5 1916.24
  5032.4 1916.96  5052.4 1926.71  5082.4 1935.97  5208.2 1951.08  5251.9 1960.74
  5257.0 1959.92  5275.4 1964.96  5300.7 1966.47  5367.5 1974.04  5450.4 1979.26
#Mann=7,-1,0
  4594.6   0.035       0  4624.9    0.07       0  4727.7   0.035       0
  4798.5     0.1       0  4926.1    0.07       0  5010.3    0.05       0
  5014.5    0.07       0
Bank Sta=5010.3,5014.5
Exp/Cntr=0.3,0.1

Type RM Length L Ch R = 1,122,0,0,0
BEGIN DESCRIPTION:
White Oak Creek 0.1
END DESCRIPTION:
XS GIS Cut Line= 4
      1836789.77     13912041.52      1836562.07     13911980.53
      1836434.61     13911984.20      1836191.08     13912040.08
#Sta/Elev= 30
  4718.1 1976.03  4733.7 1974.91  4835.8 1971.51  4875.9 1969.10  4910.2 1965.24
  4940.4 1960.54  4949.7 1957.90  4953.8 1957.90  4970.9 1949.65  4980.9 1942.46
  4990.9 1937.82  5010.9 1925.81  5020.9 1917.90  5028.8 1915.06  5029.1 1914.56
  5033.0 1915.06  5050.9 1915.20  5060.9 1917.07  5083.7 1915.63  5091.2 1917.37
  5106.9 1923.42  5132.2 1925.70  5163.0 1931.57  5192.7 1935.36  5204.1 1937.80
  5234.8 1940.24  5245.8 1942.77  5275.9 1945.91  5283.6 1947.87  5331.2 1955.95
#Mann=5,-1,0
  4718.1    0.07       0  4733.7     0.1       0  4910.2    0.07       0
  5028.8    0.05       0  5033.0    0.07       0
Bank Sta=5028.8,5033
Exp/Cntr=0.3,0.1

Chan Stop Cuts=-1