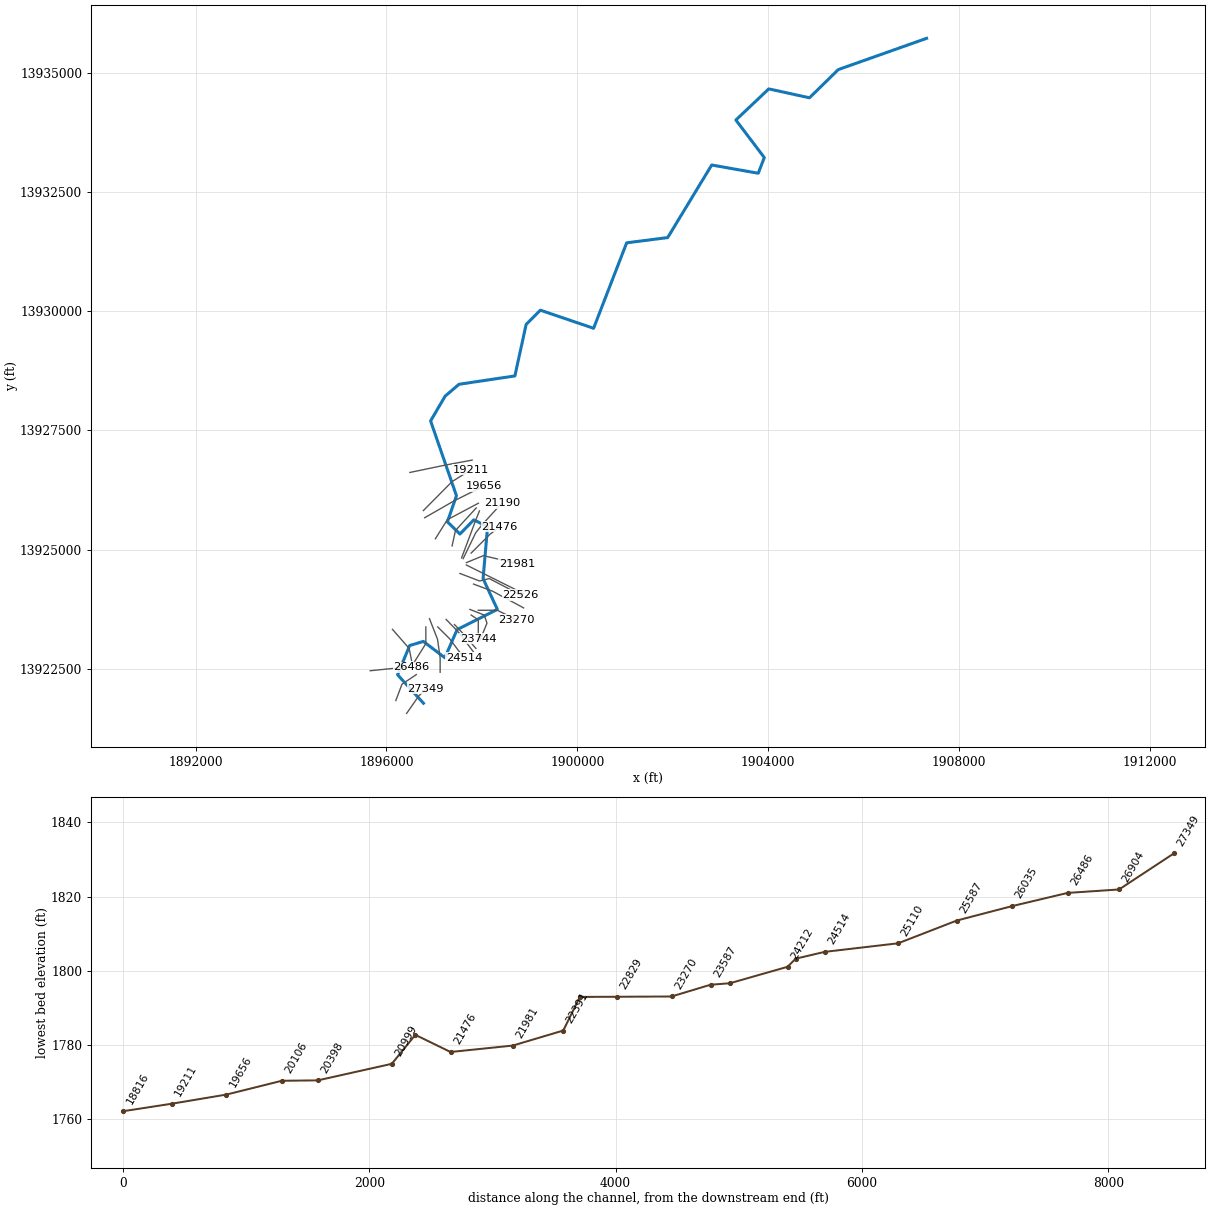
--- Bear Creek.prj (project) ---

Proj Title=Bear Creek_US Base Level Engineering
Current Plan=p01
Default Exp/Contr=0.3,0.1
English Units
Geom File=g01
Flow File=f01
Plan File=p01
Y Axis Title=Elevation
X Axis Title(PF)=Main Channel Distance
X Axis Title(XS)=Station
BEGIN DESCRIPTION:
Bear Creek
END DESCRIPTION:
DSS Export Rating Curves= 0
DSS Export Rating Curve Sorted= 0
DSS Export Volume Flow Curves= 0
DXF OffsetX= 0
DXF OffsetY= 0
DXF ScaleX= 1
DXF ScaleY= 10

--- Bear Creek.p01 (plan) ---

Plan Title=Multiple Run
Program Version=4.10
Short Identifier=Multiple
Geom File=g01
Flow File=f01
Subcritical Flow
K Sum by GR= 0
Std Step Tol= 0.01
Critical Tol= 0.01
Num of Std Step Trials= 20
Max Error Tol= 0.3
Flow Tol Ratio= 0.001
Split Flow NTrial= 30
Split Flow Tol= 0.02
Split Flow Ratio= 0.02
Log Output Level= 0
Friction Slope Method= 1
Unsteady Friction Slope Method= 2
Unsteady Bridges Friction Slope Method= 1
Parabolic Critical Depth
Global Vel Dist= 1 , 1 , 1
Global Log Level= 0
CheckData=True
Encroach Param=-1 ,0,0, 0
BEGIN DESCRIPTION:
Multiple Run
END DESCRIPTION:
Computation Interval=1HOUR
Output Interval=1HOUR
Run HTab= 0
Run UNet= 0
Run PostProcess= 0
Run WQNet= 0
UNET Theta= 1
UNET Theta Warmup= 1
UNET ZTol= 0.02
UNET ZSATol= 0.05
UNET MxIter= 20
UNET MaxInSteps= 0
UNET DtIC= 0
UNET DtMin= 0
UNET MaxCRTS= 20
UNET WFStab= 2
UNET SFStab= 1
UNET WFX= 1
UNET SFX= 1
UNET DSS MLevel= 4
UNET DZMax Abort= 100
UNET Convert EG Bridges= 0
UNET Use Existing IB Tables=-1
UNET Froude Reduction=False
UNET Froude Limit= 1
UNET Froude Power= 10
UNET Time Slicing=0,0, 5
UNET Junction Losses=0
Instantaneous Interval=1HOUR
Write IC File= 0
Write IC File at Sim End=0
Echo Input=False
Echo Parameters=False
Echo Output=False
Write Detailed= 0
WQ AD Non Conservative
WQ ULTIMATE=-1
WQ Max Comp Step=1HOUR
WQ Output Interval=15MIN
WQ Output Selected Increments= 0
WQ Output face flow=0
WQ Output face velocity=0
WQ Output face area=0
WQ Output face dispersion=0
WQ Output cell volume=0
WQ Output cell surface area=0
WQ Output cell continuity=0
WQ Output cumulative cell continuity=0
WQ Output face conc=0
WQ Output face dconc_dx=0
WQ Output face courant=0
WQ Output face peclet=0
WQ Output face adv mass=0
WQ Output face disp mass=0
WQ Output cell mass=0
WQ Output cell source sink temp=0
WQ Output cell source sink nsm=0
WQ Output MaxMinRange=-1
WQ Daily Max Min Mean=-1
WQ Daily Range=0
WQ Daily Time=0
WQ Create Restart=0
WQ Fixed Restart=0
WQ System Summary=0
WQ Use Fixed Temperature=0
Sorting and Armoring Iterations= 10
XS Update Threshold= 0.02
Hydraulics Update Threshold= 0.02
Energy Slope Method= 1
Volume Change Method= 0
XS Weighting Method= 0
Number of US Weighted Cross Sections= 1
Number of DS Weighted Cross Sections= 1
Upstream XS Weight=0.25
Main XS Weight=0.5
Downstream XS Weight=0.25
Number of DS XS's Weighted with US Boundary= 1
Upstream Boundary Weight= 1
Weight of XSs Associated with US Boundary= 0
Number of US XS's Weighted with DS Boundary= 1
Downstream Boundary Weight= 0.5
Weight of XSs Associated with DS Boundary= 0.5
Sediment Output Level= 4
Mass or Volume Output= 0
Output Increment Type= 1
Profile and TS Output Increment= 10
XS Output Flag= 0
XS Output Increment= 10
Disregard all LS=0
Disregard all Conn=0
Disregard all Breaches=0
Disregard all Pumps=0

--- Bear Creek.f01 (steady flow) ---

Flow Title=Multiple
Program Version=4.10
Number of Profiles= 7
Profile Names=10-year,25-year,50-year,1pct_min,100-year,1pct_plu,500-year
River Rch & RM=Bear Creek,Reach-1         ,27349
    1340    2304    3229    2187    4363    8706    7868
River Rch & RM=Bear Creek,Reach-1         ,26486
    2387    4226    6039    4160    8301   16563   15502
River Rch & RM=Bear Creek,Reach-1         ,23270
    3186    5709    8222    5702   11377   22700   21539
River Rch & RM=Bear Creek,Reach-1         ,18279
    3481    6263    9045    6287   12544   25029   23862
River Rch & RM=Bear Creek,Reach-1         ,17369
    3785    6823    9867    6866   13699   27332   26110
River Rch & RM=Bear Creek,Reach-1         ,12985
    4243    7679   11133    7762   15488   30902   29647
River Rch & RM=Bear Creek,Reach-1         ,9237
    4776    8684   12630    8831   17620   35157   33918
River Rch & RM=Bear Creek,Reach-1         ,7389
    5110    9302   13537    9468   18891   37693   36389
River Rch & RM=Bear Creek,Reach-1         ,1416
    5131    9336   13583    9497   18949   37809   36476
Boundary for River Rch & Prof#=Bear Creek,Reach-1         , 1
Up Type= 0
Dn Type= 3
Dn Slope=0.007
Boundary for River Rch & Prof#=Bear Creek,Reach-1         , 2
Up Type= 0
Dn Type= 3
Dn Slope=0.007
Boundary for River Rch & Prof#=Bear Creek,Reach-1         , 3
Up Type= 0
Dn Type= 3
Dn Slope=0.007
Boundary for River Rch & Prof#=Bear Creek,Reach-1         , 4
Up Type= 0
Dn Type= 3
Dn Slope=0.007
Boundary for River Rch & Prof#=Bear Creek,Reach-1         , 5
Up Type= 0
Dn Type= 3
Dn Slope=0.007
Boundary for River Rch & Prof#=Bear Creek,Reach-1         , 6
Up Type= 0
Dn Type= 3
Dn Slope=0.007
Boundary for River Rch & Prof#=Bear Creek,Reach-1         , 7
Up Type= 0
Dn Type= 3
Dn Slope=0.007
DSS Import GetInterval= 0
DSS Import GetPeak= 0
DSS Import FillOption= 0

--- Bear Creek.g01 (geometry) ---

Geom Title=Existing Conditions
Program Version=4.10

River Reach=Bear Creek      ,Reach-1
Reach XY= 30
        1896775.       13921775.      1896232.55     13922371.74
      1896485.61     13922985.06      1896773.37     13923071.87
      1897223.45     13922728.75      1897480.47     13923319.74
      1898324.93     13923743.23       1898025.1     13924389.04
      1898119.48     13925477.43      1897830.45     13925622.84
      1897540.36     13925324.89      1897277.08     13925580.48
      1897466.92      13926128.3      1896924.52     13927697.84
      1897230.62     13928219.38      1897521.67     13928467.02
      1898691.71     13928641.64      1898928.46     13929723.75
       1899226.5     13930021.54      1900342.06     13929641.48
      1901035.78     13931434.68      1901895.58     13931544.58
      1902818.78     13933067.27      1903795.17      13932894.6
      1903921.47     13933223.54      1903325.65     13934011.08
      1904015.32     13934664.24      1904869.06     13934477.26
       1905472.7     13935069.17        1907325.       13935725.

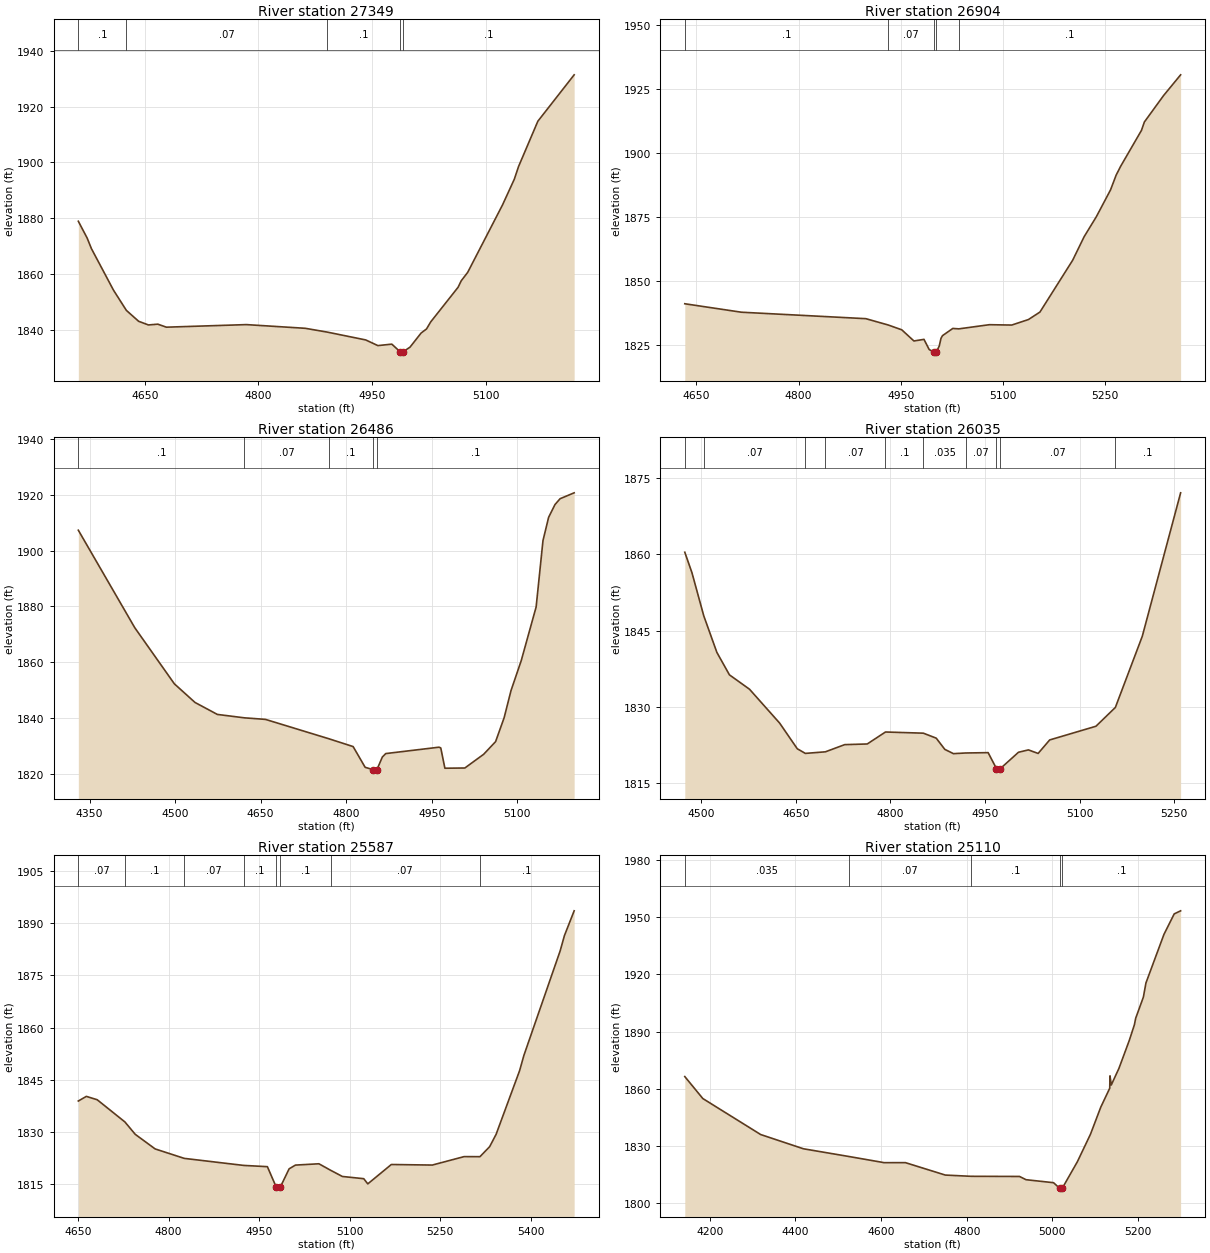
Type RM Length L Ch R = 1 ,27349   ,445,445,445
BEGIN DESCRIPTION:
Bear Creek 58.0
END DESCRIPTION:
XS GIS Cut Line= 3
      1896422.58     13921561.97        1896675.       13921925.
        1896825.       13922075.
#Sta/Elev= 30
  4562.3  1878.9    4574 1872.84  4579.5 1869.13  4608.7  1854.2  4625.7 1846.95
  4641.9 1843.04  4654.8 1841.73  4667.2 1842.01  4678.5 1840.93  4784.1 1841.85
  4861.7 1840.53  4890.9 1839.16  4941.5 1836.36  4957.6 1834.33    4976 1834.85
  4986.9 1832.13  4987.1 1831.63  4990.9 1832.13    5000 1833.77  5014.6 1838.82
  5021.8  1840.3  5027.3 1842.82  5063.4 1855.22  5067.6 1857.56  5076.1 1860.57
    5122 1884.71  5137.6 1893.95  5143.2 1898.49  5168.7 1914.75  5216.6 1931.38
#Mann= 5 ,-1 , 0
  4562.3      .1       0  4625.7     .07       0  4890.9      .1       0
  4986.9     .05       0  4990.9      .1       0
Bank Sta=4986.9,4990.9
XS Rating Curve= 0 ,0
Exp/Cntr=0.3,0.1

Type RM Length L Ch R = 1 ,26904   ,418,418,418
BEGIN DESCRIPTION:
Bear Creek 57.0
END DESCRIPTION:
XS GIS Cut Line= 3
      1896195.81     13921831.28        1896325.       13922175.
      1896625.04     13922375.03
#Sta/Elev= 30
    4633 1841.17  4716.1 1837.87  4898.8 1835.35    4932 1832.85  4951.5    1831
  4969.3 1826.65  4984.1 1827.28  4991.8 1823.28  4998.4 1822.41  4998.7 1821.91
  5002.4 1822.41  5006.5 1824.68  5009.1 1827.72  5011.3 1828.73  5026.4 1831.54
  5035.3 1831.38    5080    1833  5112.9 1832.86  5137.4 1835.01  5154.3 1837.93
  5202.3 1858.13  5219.2 1867.34  5237.2 1875.18  5257.9 1885.58  5266.1 1891.31
  5272.6 1894.72  5303.3  1908.8  5307.6 1912.08  5335.8  1922.4  5360.8 1930.48
#Mann= 5 ,-1 , 0
    4633      .1       0    4932     .07       0  4998.4     .05       0
  5002.4     .07       0  5035.3      .1       0
Bank Sta=4998.4,5002.4
XS Rating Curve= 0 ,0
Exp/Cntr=0.3,0.1

Type RM Length L Ch R = 1 ,26486   ,451,451,451
BEGIN DESCRIPTION:
Bear Creek 56.0
END DESCRIPTION:
XS GIS Cut Line= 3
      1895658.65      13922456.3        1896325.       13922525.
      1896525.01       13922525.
#Sta/Elev= 30
  4330.1 1907.31  4429.2 1872.35  4498.6 1852.26  4534.8 1845.59    4574  1841.3
  4621.4 1840.08  4658.4 1839.52  4769.5 1832.59  4812.2 1829.78  4833.3 1822.35
  4847.8 1821.48  4848.3 1820.98  4853.9 1821.48  4863.5 1826.04  4869.5 1827.27
    4963 1829.56    4966 1829.29  4973.2 1822.02  5008.2  1822.1  5041.2 1827.01
  5062.2 1831.56  5077.2 1840.15  5089.2 1849.84  5107.2 1860.61  5133.3 1879.82
  5145.3 1903.58  5155.2 1911.93  5166.3 1916.49  5175.3  1918.6    5200 1920.71
#Mann= 5 ,-1 , 0
  4330.1      .1       0  4621.4     .07       0  4769.5      .1       0
  4847.8     .05       0  4853.9      .1       0
Bank Sta=4847.8,4853.9
XS Rating Curve= 0 ,0
Exp/Cntr=0.3,0.1

Type RM Length L Ch R = 1 ,26035   ,448,448,448
BEGIN DESCRIPTION:
Bear Creek 55.0
END DESCRIPTION:
XS GIS Cut Line= 3
      1896125.01     13923324.98        1896475.       13922925.
      1896524.99     13922675.04
#Sta/Elev= 30
  4473.8 1860.39  4485.1 1856.39  4503.9  1847.9  4524.7 1840.72  4544.6 1836.32
  4576.5 1833.49  4624.3 1826.84  4652.2 1821.81    4665  1820.9  4696.8 1821.21
  4727.4 1822.62  4763.2 1822.75  4792.1  1825.1  4852.2 1824.87  4872.6 1823.89
  4886.2 1821.69  4899.9 1820.85  4919.3 1820.98  4954.9 1821.05  4968.1 1817.92
  4968.6 1817.42  4974.3 1817.92    5003 1821.12  5018.8 1821.59  5034.2 1820.89
  5052.5 1823.54  5125.9 1826.23  5156.7 1829.92  5199.4 1843.89  5260.2 1872.05
#Mann= 10 ,-1 , 0
  4473.8      .1       0  4503.9     .07       0    4665      .1       0
  4696.8     .07       0  4792.1      .1       0  4852.2    .035       0
  4919.3     .07       0  4968.1     .05       0  4974.3     .07       0
  5156.7      .1       0
Bank Sta=4968.1,4974.3
XS Rating Curve= 0 ,0
Exp/Cntr=0.3,0.1

Type RM Length L Ch R = 1 ,25587   ,477,477,477
BEGIN DESCRIPTION:
Bear Creek 54.0
END DESCRIPTION:
XS GIS Cut Line= 3
        1896825.     13923375.01        1896825.       13923025.
      1896575.01     13922625.01
#Sta/Elev= 30
  4650.4 1838.88  4663.7 1840.21  4681.7 1839.24  4727.6 1832.86  4744.7  1829.3
  4777.7  1825.1    4826 1822.38  4924.3 1820.36  4963.7    1820  4978.6 1814.04
  4979.1 1813.54  4984.9 1814.04  4999.7 1819.37  5010.2 1820.45  5049.1 1820.83
  5068.3 1818.98    5088 1817.18  5123.4 1816.54  5130.1 1815.05  5169.1 1820.62
    5237 1820.46  5289.7 1822.89    5316 1822.87  5332.1 1825.76  5342.8 1829.32
  5381.7 1847.61  5388.8    1852  5448.9 1882.05    5456 1886.45  5472.1 1893.57
#Mann= 8 ,-1 , 0
  4650.4     .07       0  4727.6      .1       0    4826     .07       0
  4924.3      .1       0  4978.6     .05       0  4984.9      .1       0
  5068.3     .07       0    5316      .1       0
Bank Sta=4978.6,4984.9
XS Rating Curve= 0 ,0
Exp/Cntr=0.3,0.1

Type RM Length L Ch R = 1 ,25110   ,596,596,596
BEGIN DESCRIPTION:
Bear Creek 53.0
END DESCRIPTION:
XS GIS Cut Line= 4
      1896901.63     13923547.91      1897070.24     13923115.27
        1897125.       13922725.        1897125.     13922425.13
#Sta/Elev= 30
  4141.4  1866.4  4183.5 1854.88  4318.7 1836.01  4418.5 1828.55  4525.9 1824.46
  4607.2 1821.27  4656.8 1821.28    4750 1814.77  4809.9 1814.12  4923.4 1814.04
  4938.5 1812.34  5002.8 1810.77  5016.9  1807.9  5017.4  1807.4  5023.3  1807.9
  5058.5 1821.77  5089.1 1836.17  5113.1 1850.33  5134.1 1860.29  5134.7 1866.78
  5137.7 1861.98  5155.7 1870.76  5179.7  1885.3  5191.7 1893.54  5194.7 1896.96
  5212.7 1908.05  5218.7 1915.48  5260.7  1940.9  5284.7 1951.67  5299.7 1953.28
#Mann= 5 ,-1 , 0
  4141.4    .035       0  4525.9     .07       0  4809.9      .1       0
  5016.9     .05       0  5023.3      .1       0
Bank Sta=5016.9,5023.3
XS Rating Curve= 0 ,0
Exp/Cntr=0.3,0.1

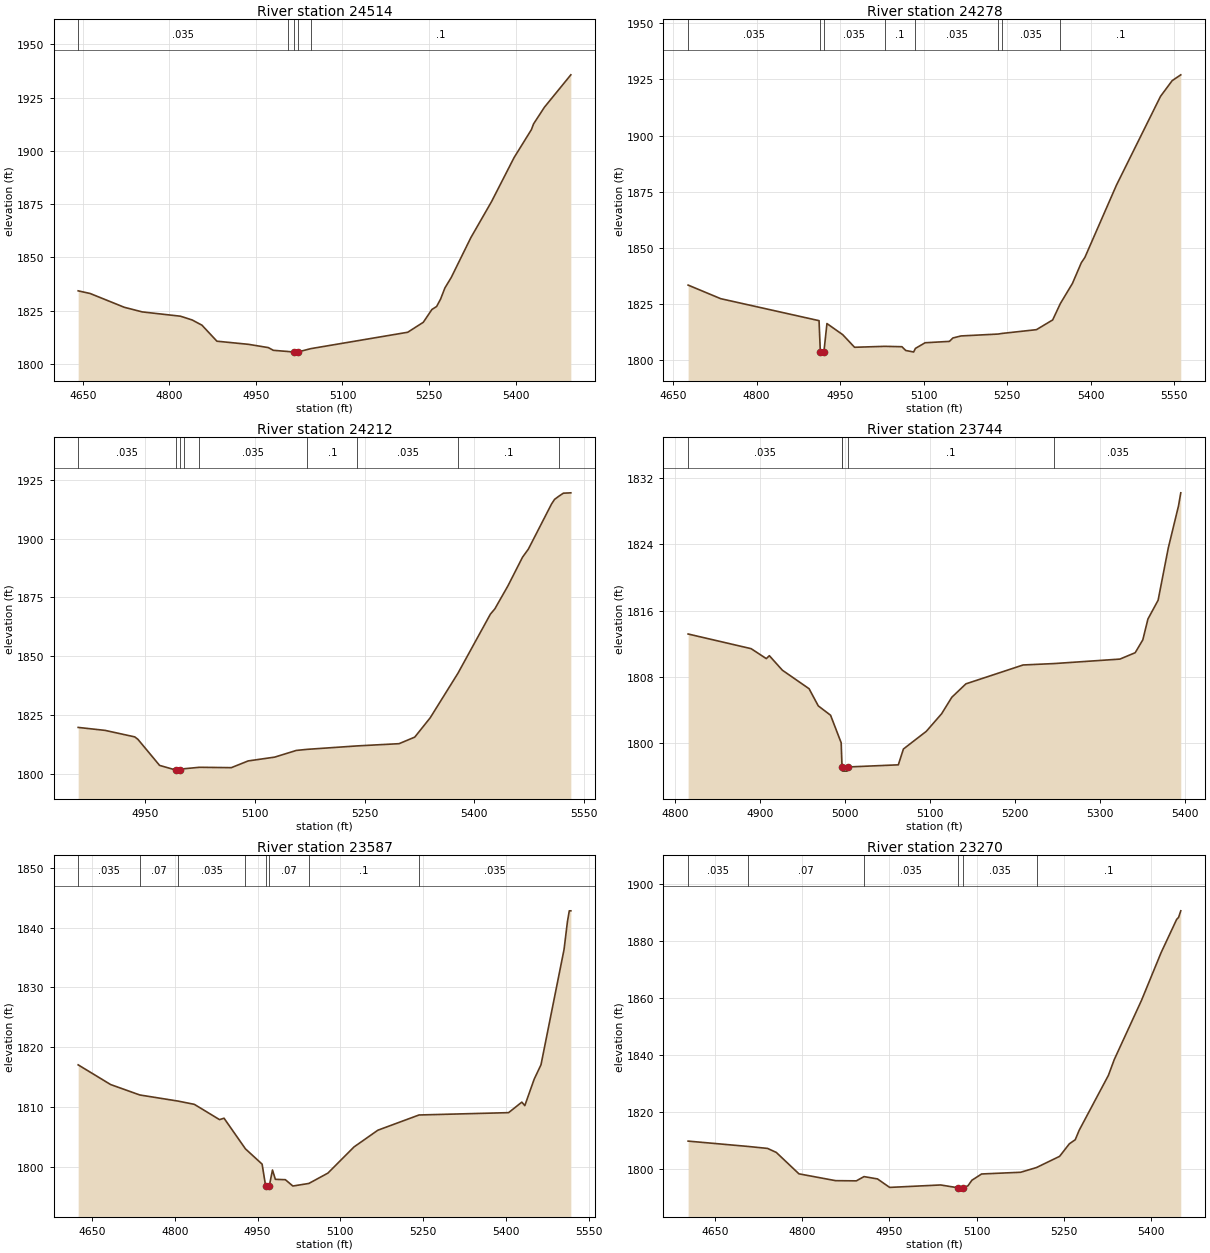
Type RM Length L Ch R = 1 ,24514   ,236,236,236
BEGIN DESCRIPTION:
Bear Creek 52.0
END DESCRIPTION:
XS GIS Cut Line= 3
      1897074.97     13923375.03       1897324.1     13923126.97
      1897625.01     13922724.99
#Sta/Elev= 30
    4642 1834.31  4662.7 1833.07  4721.9  1826.6    4753 1824.43  4819.3 1822.41
  4839.5 1820.65  4856.5  1818.2  4882.4 1810.69  4937.3 1809.21  4971.5 1807.68
  4980.2 1806.41  5005.7 1805.85  5015.7 1805.59  5016.2 1805.09  5022.1 1805.59
  5045.2  1807.2    5213 1814.88    5240 1819.55    5255 1825.58  5263.1 1826.96
    5270 1830.45  5277.5 1835.68  5288.5  1840.6  5322.4 1859.25  5358.2 1876.13
  5397.4 1896.86  5427.4 1909.96  5431.1 1912.63  5449.9 1920.45  5495.7 1935.66
#Mann= 5 ,-1 , 0
    4642    .035       0  5005.7     .07       0  5015.7    .035       0
  5022.1     .07       0  5045.2      .1       0
Bank Sta=5015.7,5022.1
XS Rating Curve= 0 ,0
Exp/Cntr=0.3,0.1

Type RM Length L Ch R = 1 ,24278   ,66,66,66
BEGIN DESCRIPTION:
Bear Creek D4
END DESCRIPTION:
XS GIS Cut Line= 4
      1897250.37     13923533.13      1897464.15     13923312.84
      1897533.59     13923237.97      1897818.97     13922857.11
#Sta/Elev= 30
  4677.1  1833.5  4735.6 1827.46  4912.3 1817.68  4914.6 1803.75  4915.1 1803.25
    4921 1803.75  4926.5 1816.39  4954.8 1811.46  4976.1 1805.85  5030.5 1806.27
  5061.2  1806.1    5068 1804.43  5082.2 1803.75  5085.4 1805.35  5102.8 1807.86
  5146.5 1808.47  5152.8 1809.99  5167.3 1810.89    5234 1811.73  5241.2 1812.01
  5302.8 1813.68    5332 1818.01  5345.7 1825.26  5367.4  1834.2  5383.5 1843.48
  5389.8 1845.79  5446.6 1877.96  5525.7 1917.41  5546.6 1924.39  5562.1 1926.98
#Mann= 8 ,-1 , 0
  4677.1    .035       0  4914.6    .035       0    4921    .035       0
  5030.5      .1       0  5085.4    .035       0    5234      .1       0
  5241.2    .035       0  5345.7      .1       0
Bank Sta=4914.6,4921
XS Rating Curve= 0 ,0
Exp/Cntr=0.3,0.1

Type RM Length L Ch R = 1 ,24212   ,468,468,468
BEGIN DESCRIPTION:
Bear Creek 51.0
END DESCRIPTION:
XS GIS Cut Line= 3
        1897425.       13923425.        1897525.       13923325.
      1897874.99     13922925.02
#Sta/Elev= 30
  4858.8 1819.66  4895.5  1818.4    4936 1815.64  4940.3 1814.63    4970  1803.5
  4991.8 1801.56  4992.3 1801.06  4998.2 1801.56  5003.7 1802.08  5024.5 1802.69
    5068 1802.54    5091  1805.4  5127.2 1807.02  5156.8 1809.87  5171.6 1810.33
  5240.3  1811.8  5297.1 1812.74  5318.5 1815.53  5339.6 1823.75  5377.5 1842.71
  5421.8 1867.85  5427.9 1870.11  5445.8 1879.91  5465.7 1892.09  5473.7 1895.54
  5505.3 1914.72  5509.5 1916.71    5515 1917.98  5521.5 1919.34  5531.7 1919.49
#Mann= 9 ,-1 , 0
  4858.8    .035       0  4991.8    .035       0  4998.2    .035       0
  5003.7      .1       0  5024.5    .035       0  5171.6      .1       0
  5240.3    .035       0  5377.5      .1       0    5515     .07       0
Bank Sta=4991.8,4998.2
XS Rating Curve= 0 ,0
Exp/Cntr=0.3,0.1

Type RM Length L Ch R = 1 ,23744   ,157,157,157
BEGIN DESCRIPTION:
Bear Creek 50.0
END DESCRIPTION:
XS GIS Cut Line= 3
      1897775.02     13923624.99        1897925.       13923525.
        1897925.     13923124.96
#Sta/Elev= 30
    4815 1813.19  4889.2 1811.42  4907.1 1810.22  4910.7 1810.57    4926 1808.82
  4957.5 1806.58  4968.3 1804.51  4982.8 1803.38  4995.3 1800.05  4996.1 1797.71
  4996.3 1797.13  4996.8 1796.63  5002.3 1796.63  5002.8 1797.13  5062.6 1797.39
  5068.6  1799.3  5095.6 1801.44  5113.6 1803.56  5125.6 1805.55  5142.2 1807.17
  5209.6 1809.45  5246.2 1809.62  5323.6 1810.16  5341.6 1810.93  5350.6 1812.49
  5356.6    1815  5368.6 1817.27  5380.6 1823.59  5392.6 1828.65  5395.3 1830.24
#Mann= 5 ,-1 , 0
    4815    .035       0  4996.1      .1       0  4996.3     .05       0
  5002.8      .1       0  5246.2    .035       0
Bank Sta=4996.3,5002.8
XS Rating Curve= 0 ,0
Exp/Cntr=0.3,0.1

Type RM Length L Ch R = 1 ,23587   ,317,317,317
BEGIN DESCRIPTION:
Bear Creek D3
END DESCRIPTION:
XS GIS Cut Line= 4
      1897749.25     13923743.29      1898050.09     13923624.25
      1898106.51      13923453.9      1897957.85     13923093.65
#Sta/Elev= 30
    4625 1817.03  4683.9 1813.73  4736.6 1811.99  4805.7 1810.97  4835.5 1810.42
  4881.2 1807.86  4889.3  1808.1  4928.1 1802.97  4958.3 1800.41  4964.7 1796.73
  4965.2 1796.23  4971.2 1796.73  4977.1 1799.43  4982.3 1797.87  5000.4 1797.81
    5014 1796.75    5043 1797.18  5077.5 1798.91  5124.8 1803.29    5168 1806.09
  5242.6 1808.64  5404.9 1809.03  5428.9 1810.79  5434.3 1810.21  5451.3 1814.64
  5463.6 1817.04  5505.4 1836.34  5511.5 1840.98  5514.9 1842.81  5517.7 1842.81
#Mann= 8 ,-1 , 0
    4625    .035       0  4736.6     .07       0  4805.7    .035       0
  4928.1     .07       0  4964.7     .05       0  4971.2     .07       0
    5043      .1       0  5242.6    .035       0
Bank Sta=4964.7,4971.2
XS Rating Curve= 0 ,0
Exp/Cntr=0.3,0.1

Type RM Length L Ch R = 1 ,23270   ,441,441,441
BEGIN DESCRIPTION:
Bear Creek 49.0
END DESCRIPTION:
XS GIS Cut Line= 3
      1897924.98       13923725.        1898325.       13923725.
      1898724.97     13923525.01
#Sta/Elev= 30
  4603.9 1809.89    4707 1808.02  4740.5 1807.33  4755.5 1805.93  4794.5 1798.42
  4857.5 1796.03  4893.2 1795.96  4906.4 1797.45  4929.5 1796.64  4950.5 1793.66
  5038.1 1794.52  5067.2 1793.56  5067.7 1793.06  5076.1 1793.56  5085.1 1794.22
  5091.8 1796.16  5108.6 1798.37  5175.7 1798.97    5203 1800.63  5242.7 1804.55
  5259.5 1808.95  5269.6 1810.37  5276.3 1813.66  5326.6 1832.92  5336.7 1838.47
  5383.6 1859.25  5417.2 1875.93    5444 1887.61  5447.3  1888.3  5451.1 1890.61
#Mann= 6 ,-1 , 0
  4603.9    .035       0    4707     .07       0  4906.4    .035       0
  5067.2    .035       0  5076.1    .035       0    5203      .1       0
Bank Sta=5067.2,5076.1
XS Rating Curve= 0 ,0
Exp/Cntr=0.3,0.1

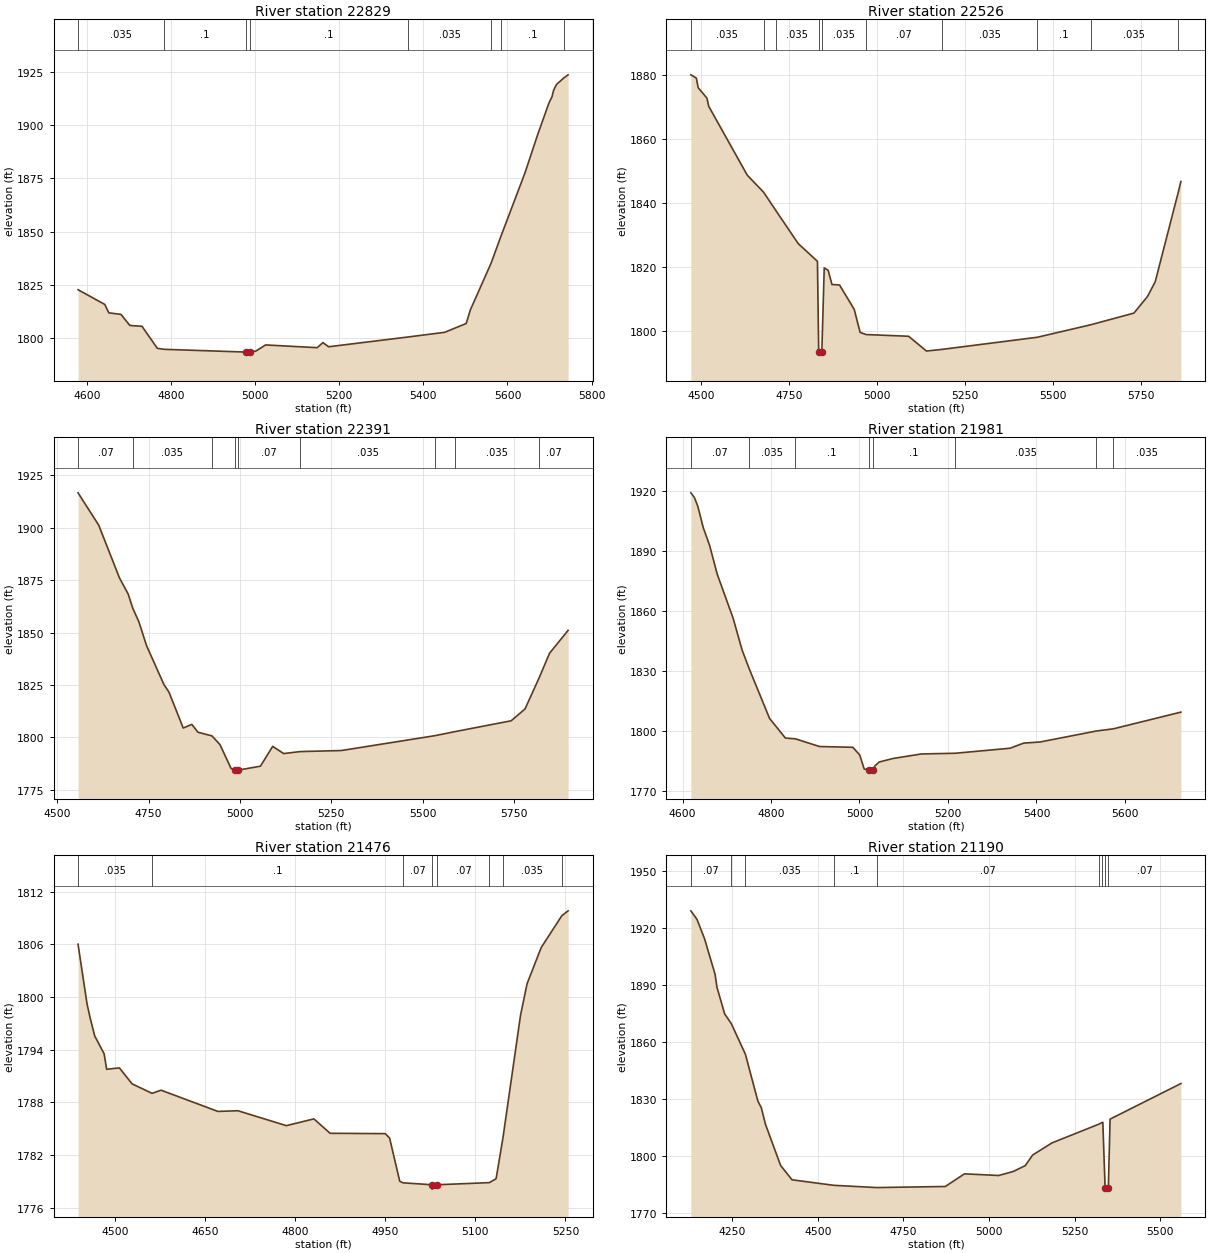
Type RM Length L Ch R = 1 ,22829   ,303,303,303
BEGIN DESCRIPTION:
Bear Creek 48.0
END DESCRIPTION:
XS GIS Cut Line= 3
      1897825.03     13924274.99        1898225.       13924125.
      1898874.99       13923775.
#Sta/Elev= 30
  4578.8 1822.74  4642.4 1815.83    4652 1811.88  4680.9 1811.17  4702.1 1805.96
  4730.9 1805.58  4767.4 1795.23  4784.3 1794.77  4977.6 1793.49  4978.1 1792.99
  4986.6 1793.49  5001.3 1793.91  5024.8 1796.83  5147.5 1795.55  5161.1 1797.92
  5174.8 1795.98  5363.3 1800.55  5450.7 1802.75  5501.8 1806.88  5512.1 1813.41
  5561.1 1835.19  5584.8 1847.97  5641.5 1877.45  5672.2 1895.68  5699.1 1910.55
  5705.8 1913.15  5709.7 1916.26  5716.5 1918.98  5734.2 1922.13  5744.2 1923.54
#Mann= 8 ,-1 , 0
  4578.8    .035       0  4784.3      .1       0  4977.6     .05       0
  4986.6      .1       0  5363.3    .035       0  5561.1     .07       0
  5584.8      .1       0  5734.2     .07       0
Bank Sta=4977.6,4986.6
XS Rating Curve= 0 ,0
Exp/Cntr=0.3,0.1

Type RM Length L Ch R = 1 ,22526   ,135,135,135
BEGIN DESCRIPTION:
Bear Creek D2
END DESCRIPTION:
XS GIS Cut Line= 4
       1897540.2     13924497.35      1897951.67     13924339.79
      1898154.79     13924390.57      1898813.63     13924045.53
#Sta/Elev= 30
    4470 1880.07  4485.5 1879.05  4490.9 1876.02  4515.6  1872.8  4520.9  1870.2
  4630.4 1848.66    4677  1843.3  4712.4 1837.47  4775.3 1827.24    4830 1821.69
  4833.5 1793.45    4834 1792.95  4842.5 1793.45  4849.3 1819.63  4860.6 1818.86
  4871.3 1814.43  4892.8 1814.29  4934.6 1806.64  4951.4 1799.44  4968.6 1798.76
  5089.3 1798.23    5140  1793.6  5184.5 1794.12  5455.4 1797.92  5607.1 1801.82
  5730.1 1805.48  5768.6 1810.67  5790.6 1815.28  5855.5 1843.03  5863.7  1846.7
#Mann= 10 ,-1 , 0
    4470    .035       0    4677     .07       0  4712.4    .035       0
  4833.5     .05       0  4842.5    .035       0  4968.6     .07       0
  5184.5    .035       0  5455.4      .1       0  5607.1    .035       0
  5855.5     .07       0
Bank Sta=4833.5,4842.5
XS Rating Curve= 0 ,0
Exp/Cntr=0.3,0.1

Type RM Length L Ch R = 1 ,22391   ,410,410,410
BEGIN DESCRIPTION:
Bear Creek 47.0
END DESCRIPTION:
XS GIS Cut Line= 3
      1897674.97     13924675.01        1898075.       13924475.
      1898875.03     13924074.99
#Sta/Elev= 30
  4556.9 1916.67  4613.5 1901.24  4670.5    1876    4694 1868.44    4707  1861.5
  4723.8 1854.99  4744.3 1843.82  4792.4 1825.06  4805.8  1821.6  4844.9 1804.44
  4868.4 1806.18  4885.2 1802.43  4923.5 1800.69  4945.6 1796.51  4975.8 1785.19
  4986.9 1784.38  4987.4 1783.88  4995.9 1784.38  5056.3 1786.24  5089.8 1795.69
    5120 1792.26  5165.2 1793.21  5277.6  1793.7  5533.9 1800.79  5588.1  1802.7
  5742.7 1807.89  5780.7 1813.54  5819.6 1828.51  5847.8 1840.12  5898.6 1851.04
#Mann= 9 ,-1 , 0
  4556.9     .07       0    4707    .035       0  4923.5     .07       0
  4986.9     .05       0  4995.9     .07       0  5165.2    .035       0
  5533.9      .1       0  5588.1    .035       0  5819.6     .07       0
Bank Sta=4986.9,4995.9
XS Rating Curve= 0 ,0
Exp/Cntr=0.3,0.1

Type RM Length L Ch R = 1 ,21981   ,505,505,505
BEGIN DESCRIPTION:
Bear Creek 46.0
END DESCRIPTION:
XS GIS Cut Line= 3
      1897674.98     13924724.99      1898031.58     13924871.58
      1898734.59     13924706.03
#Sta/Elev= 30
  4618.8 1919.02  4626.7 1916.73  4634.6 1912.23  4646.9 1901.54  4661.2 1892.71
  4678.5 1878.25  4714.1 1856.45  4734.8 1840.29    4751 1830.86  4796.8 1806.15
  4832.5 1796.38  4855.1 1795.99  4909.5 1792.14  4984.9 1791.75  5000.5 1787.92
  5010.6 1780.92  5021.3 1780.33  5021.8 1779.83  5030.6 1780.33  5035.2 1782.57
  5044.5 1784.38  5075.3 1786.13    5140 1788.42  5216.6 1788.77  5340.3 1791.28
  5371.2 1793.85  5408.1  1794.4  5535.7  1799.9  5573.6 1800.98  5726.6 1809.34
#Mann= 8 ,-1 , 0
  4618.8     .07       0    4751    .035       0  4855.1      .1       0
  5021.3     .05       0  5030.6      .1       0  5216.6    .035       0
  5535.7     .07       0  5573.6    .035       0
Bank Sta=5021.3,5030.6
XS Rating Curve= 0 ,0
Exp/Cntr=0.3,0.1

Type RM Length L Ch R = 1 ,21476   ,286,286,286
BEGIN DESCRIPTION:
Bear Creek 45.0
END DESCRIPTION:
XS GIS Cut Line= 3
      1897774.98     13924924.98        1898175.       13925325.
      1898374.99     13925474.99
#Sta/Elev= 30
  4438.8    1806  4453.8 1799.19  4458.8 1797.65  4466.6 1795.54  4482.2 1793.52
  4486.4 1791.75  4507.6 1791.91  4528.8 1790.09  4562.1 1789.01  4576.9 1789.37
  4671.7 1786.95  4704.9 1787.03  4785.5 1785.33  4831.4  1786.1  4858.4 1784.46
  4950.2 1784.42  4957.4 1783.92  4974.3 1778.99  4979.7 1778.82  5027.6  1778.6
  5028.1  1778.1    5037  1778.6  5123.5 1778.84  5134.7 1779.29  5146.2    1784
  5175.4 1797.93  5186.2 1801.49  5209.7 1805.61  5243.9 1809.23  5254.5  1809.8
#Mann= 8 ,-1 , 0
  4438.8    .035       0  4562.1      .1       0  4979.7     .07       0
  5027.6     .05       0    5037     .07       0  5123.5      .1       0
  5146.2    .035       0  5243.9     .07       0
Bank Sta=5027.6,5037
XS Rating Curve= 0 ,0
Exp/Cntr=0.3,0.1

Type RM Length L Ch R = 1 ,21190   ,191,191,191
BEGIN DESCRIPTION:
Bear Creek D1
END DESCRIPTION:
XS GIS Cut Line= 4
      1897607.79     13924809.07       1897872.1     13925352.85
      1898008.82     13925524.29      1898418.98     13925973.52
#Sta/Elev= 30
  4128.6  1928.9  4146.3  1924.5  4168.5 1914.27  4199.3 1895.59  4204.9 1888.76
  4227.4 1874.76  4246.8 1869.65  4288.1 1853.51  4324.2 1829.11  4334.6 1825.39
  4346.4 1816.91  4390.9 1795.15  4424.3 1787.62  4546.3 1784.72  4671.7 1783.54
  4872.2 1784.11  4928.3 1790.75  5028.2 1789.88  5070.7 1791.98  5105.9 1795.07
  5127.5 1800.63  5183.7 1806.97  5321.1 1816.85  5330.5 1817.72  5332.6 1817.81
  5339.3 1783.22  5339.8 1782.72  5348.7 1783.22  5353.8 1819.49  5560.8 1838.18
#Mann= 9 ,-1 , 0
  4128.6     .07       0  4246.8      .1       0  4288.1    .035       0
  4546.3      .1       0  4671.7     .07       0  5321.1    .035       0
  5330.5     .07       0  5339.3     .05       0  5348.7     .07       0
Bank Sta=5339.3,5348.7
XS Rating Curve= 0 ,0
Exp/Cntr=0.3,0.1

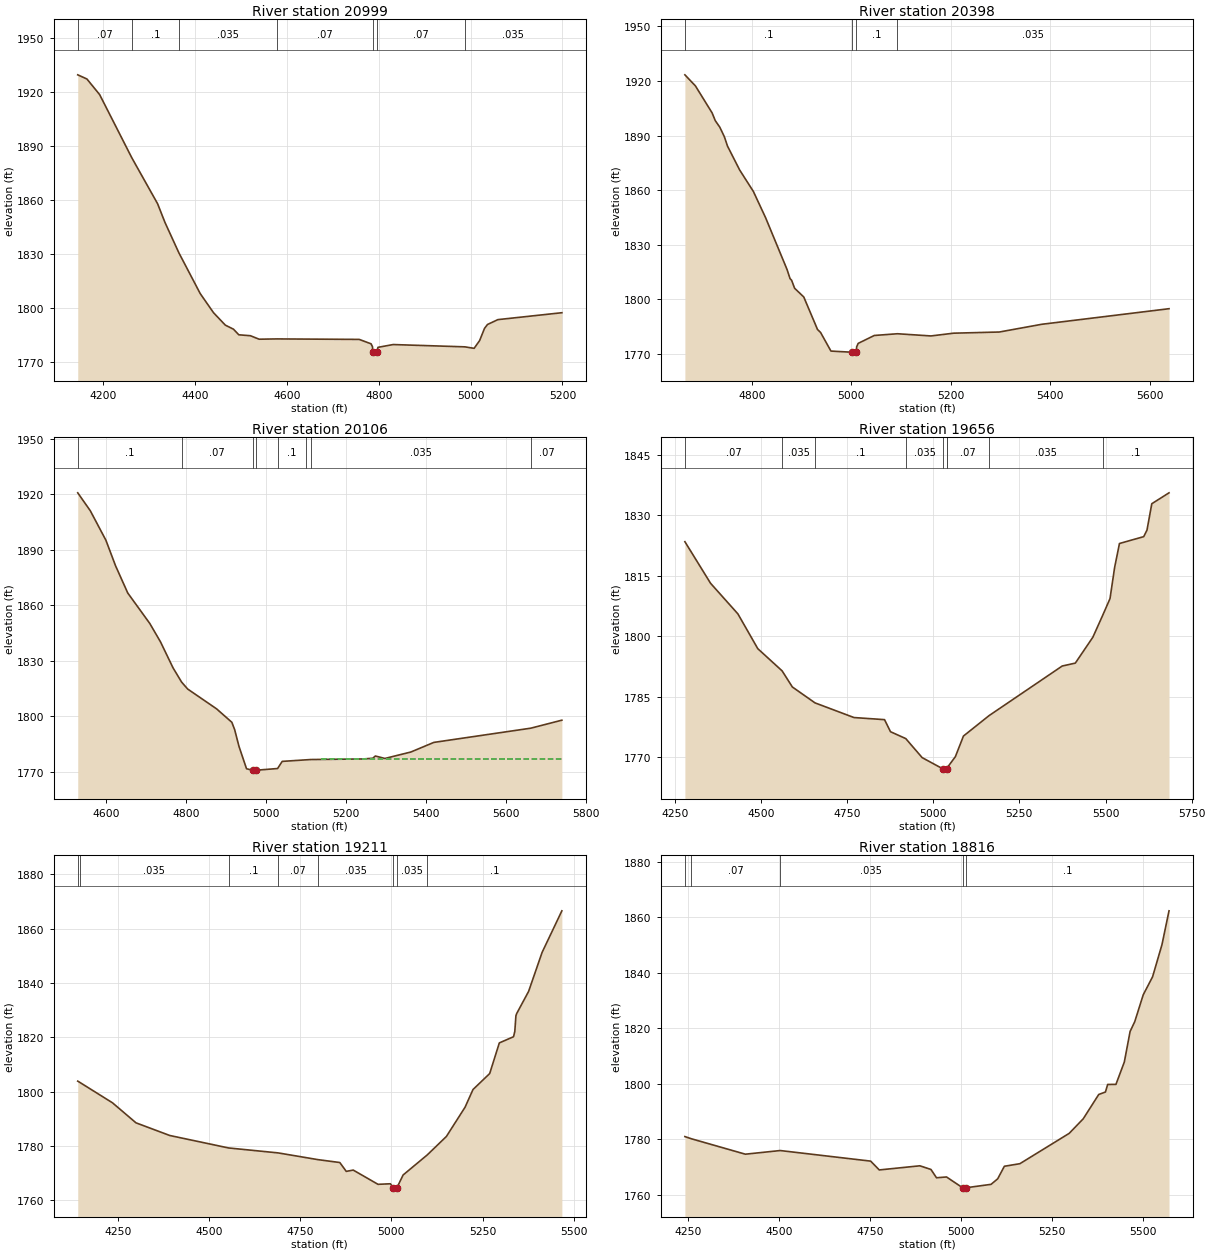
Type RM Length L Ch R = 1 ,20999   ,601,601,601
BEGIN DESCRIPTION:
Bear Creek 44.0
END DESCRIPTION:
XS GIS Cut Line= 3
      1897574.98     13924824.96        1897875.       13925625.
      1897948.88     13925810.05
#Sta/Elev= 30
    4145 1929.45    4165 1927.13  4192.7 1918.45  4262.6 1883.42  4318.8 1857.87
  4334.8 1847.51  4365.1 1830.62  4411.6 1807.96  4440.6 1797.33  4466.2 1790.46
  4483.9 1788.21  4495.6 1785.08  4520.7 1784.58  4539.8 1782.64  4578.4  1782.8
  4757.7 1782.53  4783.4 1780.08  4786.6 1778.38  4786.8 1775.41  4787.3 1774.91
  4796.2 1775.41  4798.5 1778.13  4831.4 1779.67  4987.3  1778.4  5007.7 1777.57
  5019.7 1781.89  5030.3 1788.64  5036.8 1790.81  5059.4 1793.51  5198.7 1797.35
#Mann= 7 ,-1 , 0
    4145     .07       0  4262.6      .1       0  4365.1    .035       0
  4578.4     .07       0  4786.8    .035       0  4796.2     .07       0
  4987.3    .035       0
Bank Sta=4786.8,4796.2
XS Rating Curve= 0 ,0
Exp/Cntr=0.3,0.1

Type RM Length L Ch R = 1 ,20398   ,292,292,292
BEGIN DESCRIPTION:
Bear Creek 43.0
END DESCRIPTION:
XS GIS Cut Line= 3
      1897375.01     13925075.04      1897446.37     13925399.23
      1897880.94     13925872.13
#Sta/Elev= 30
    4665 1923.38  4686.1 1917.33  4719.8 1902.45  4726.1 1898.22  4735.3 1894.58
  4744.5 1889.31  4750.7 1884.25  4775.1 1871.14  4802.9 1859.24  4827.4 1844.86
  4870.5 1816.45  4876.6  1811.4  4879.7 1810.52  4885.8 1806.09  4904.2 1801.31
  4931.9 1783.43    4938 1781.82  4958.9 1771.58  5000.5 1770.95    5001 1770.45
    5010 1770.95  5010.6  1773.9  5013.7  1775.8  5046.1 1780.15  5092.7  1781.1
  5160.2 1779.89  5205.7 1781.41  5297.7 1782.05  5383.2  1786.3  5639.2 1794.86
#Mann= 4 ,-1 , 0
    4665      .1       0  5000.5     .05       0    5010      .1       0
  5092.7    .035       0
#XS Ineff= 2 , 0
                         5082.67         1780.86
Permanent Ineff=
       F       F
Bank Sta=5000.5,5010
XS Rating Curve= 0 ,0
Exp/Cntr=0.3,0.1

Type RM Length L Ch R = 1 ,20106   ,450,450,450
BEGIN DESCRIPTION:
Bear Creek 42.0
END DESCRIPTION:
XS GIS Cut Line= 3
      1897025.01     13925225.02        1897275.       13925625.
      1897927.25     13925971.19
#Sta/Elev= 30
  4529.9 1920.89  4561.3 1911.19  4600.3 1895.24  4624.4 1881.43  4654.9  1866.7
  4709.9 1850.25  4736.7 1840.29  4768.1  1826.2  4789.5 1818.52  4804.6 1814.76
    4877 1804.02  4915.1 1796.75  4922.2 1792.72  4932.8 1783.81  4951.8 1771.61
    4967 1770.84  4967.5 1770.34  4976.5 1770.84  5029.4 1771.75    5041 1775.61
  5101.5 1776.46  5112.5 1776.61  5243.4 1776.93  5267.2 1777.31  5273.9 1778.51
  5297.7 1777.19  5362.7 1780.69    5420 1785.88  5662.3 1793.57    5740  1797.9
#Mann= 8 ,-1 , 0
  4529.9      .1       0  4789.5     .07       0    4967     .05       0
  4976.5     .07       0  5029.4      .1       0  5101.5     .07       0
  5112.5    .035       0  5662.3     .07       0
#XS Ineff= 2 , 0
                         5138.29         1776.99
Permanent Ineff=
       F       F
Bank Sta=4967,4976.5
XS Rating Curve= 0 ,0
Exp/Cntr=0.3,0.1

Type RM Length L Ch R = 1 ,19656   ,445,445,445
BEGIN DESCRIPTION:
Bear Creek 41.0
END DESCRIPTION:
XS GIS Cut Line= 3
      1896800.07     13925666.53        1897425.       13926025.
      1898037.31     13926330.66
#Sta/Elev= 30
  4279.5 1823.44  4353.9 1813.15  4433.4 1805.55    4491 1796.95  4561.7 1791.44
  4591.3 1787.46  4657.1 1783.52  4770.1 1779.89  4858.8 1779.37  4876.1 1776.38
  4920.4 1774.68  4967.9 1769.97  5029.4 1767.12  5029.9 1766.62    5039 1767.12
  5039.9 1767.38  5064.3 1770.19  5087.8 1775.31  5162.2 1780.37  5374.4 1792.65
  5412.4 1793.37  5463.3 1799.78  5491.6 1805.16  5513.1 1809.36  5526.5 1817.08
  5540.5 1822.99  5610.9 1824.69  5620.4 1826.32  5634.3 1832.84  5684.3 1835.54
#Mann= 9 ,-1 , 0
  4279.5     .07       0  4561.7    .035       0  4657.1      .1       0
  4920.4    .035       0  5029.4    .035       0    5039    .035       0
  5039.9     .07       0  5162.2    .035       0  5491.6      .1       0
Bank Sta=5029.4,5039
XS Rating Curve= 0 ,0
Exp/Cntr=0.3,0.1

Type RM Length L Ch R = 1 ,19211   ,395,395,395
BEGIN DESCRIPTION:
Bear Creek 40.0
END DESCRIPTION:
XS GIS Cut Line= 3
      1896773.24     13925817.19        1897375.       13926425.
        1897775.       13926675.
#Sta/Elev= 30
  4140.5 1803.89  4145.5 1803.49  4235.5 1795.94  4300.2 1788.55  4392.8 1783.89
  4554.1  1779.3  4689.9 1777.48  4799.1    1775  4858.8 1773.94  4876.5 1770.68
  4895.6 1771.16  4963.5 1765.92  4997.5 1766.12  5005.7 1764.65  5006.2 1764.15
  5015.4 1764.65  5032.3 1769.35  5098.5 1776.74    5151 1783.54  5202.1 1794.29
  5223.9 1800.81  5269.6 1806.68  5296.1 1817.97    5335 1820.24  5338.5  1822.2
  5341.5 1827.95  5343.6 1828.76  5376.3 1836.92  5413.3 1851.28  5467.5 1866.58
#Mann= 8 ,-1 , 0
  4140.5     .07       0  4145.5    .035       0  4554.1      .1       0
  4689.9     .07       0  4799.1    .035       0  5005.7    .035       0
  5015.4    .035       0  5098.5      .1       0
Bank Sta=5005.7,5015.4
XS Rating Curve= 0 ,0
Exp/Cntr=0.3,0.1

Type RM Length L Ch R = 1 ,18816   ,537,537,537
BEGIN DESCRIPTION:
Bear Creek 39.0
END DESCRIPTION:
XS GIS Cut Line= 3
      1896491.02     13926616.87      1897234.07     13926771.42
      1897795.33     13926875.64
#Sta/Elev= 30
  4241.7 1781.05  4259.3 1780.27  4407.8 1774.71  4503.5 1776.02    4752 1772.21
  4775.6 1769.04  4887.2 1770.53  4917.6 1769.21  4932.8 1766.22  4960.3 1766.51
  5004.5 1762.63    5005 1762.13  5014.2 1762.63  5082.6 1763.85  5100.9 1765.84
  5119.2 1770.36  5161.9 1771.29  5297.3 1782.21  5335.8 1787.44  5378.5 1796.22
  5396.8 1797.09    5403 1799.82  5425.7 1799.84  5448.7 1807.89  5464.6  1818.9
  5477.4 1822.44  5500.6 1832.08  5526.3 1838.57  5552.1 1850.13  5571.5 1862.33
#Mann= 5 ,-1 , 0
  4241.7    .035       0  4259.3     .07       0  4503.5    .035       0
  5004.5    .035       0  5014.2      .1       0
Bank Sta=5004.5,5014.2
XS Rating Curve= 0 ,0
Exp/Cntr=0.3,0.1