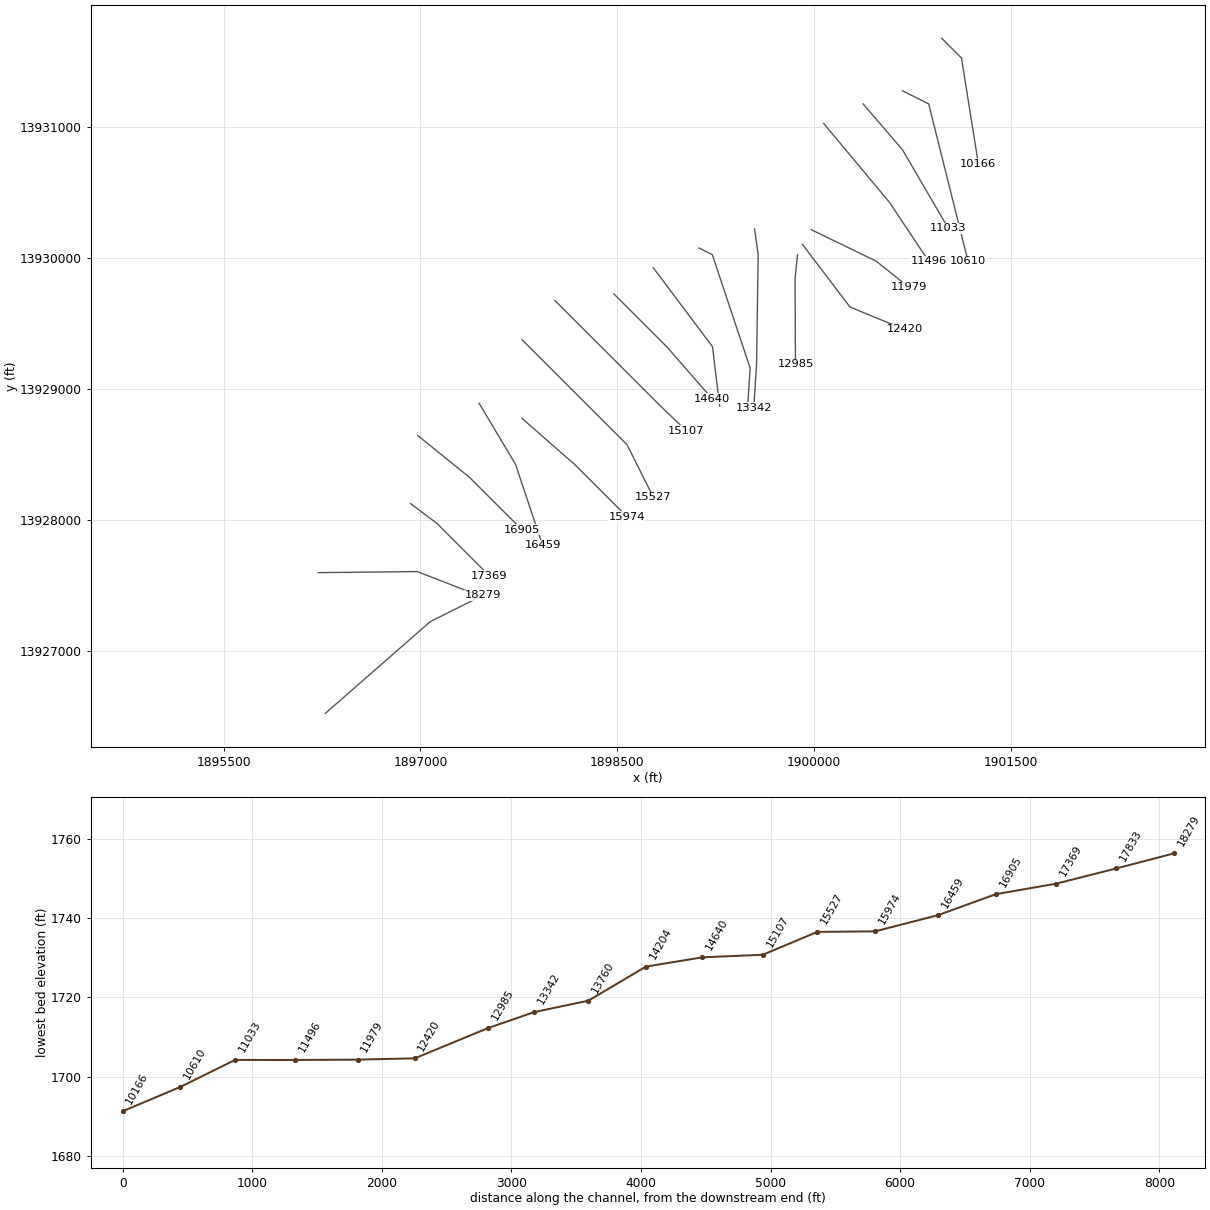
HEC-RAS study Bear Creek.prj: Bear Creek_US Base Level Engineering

--- Bear Creek.g01 (geometry) --- (continued)

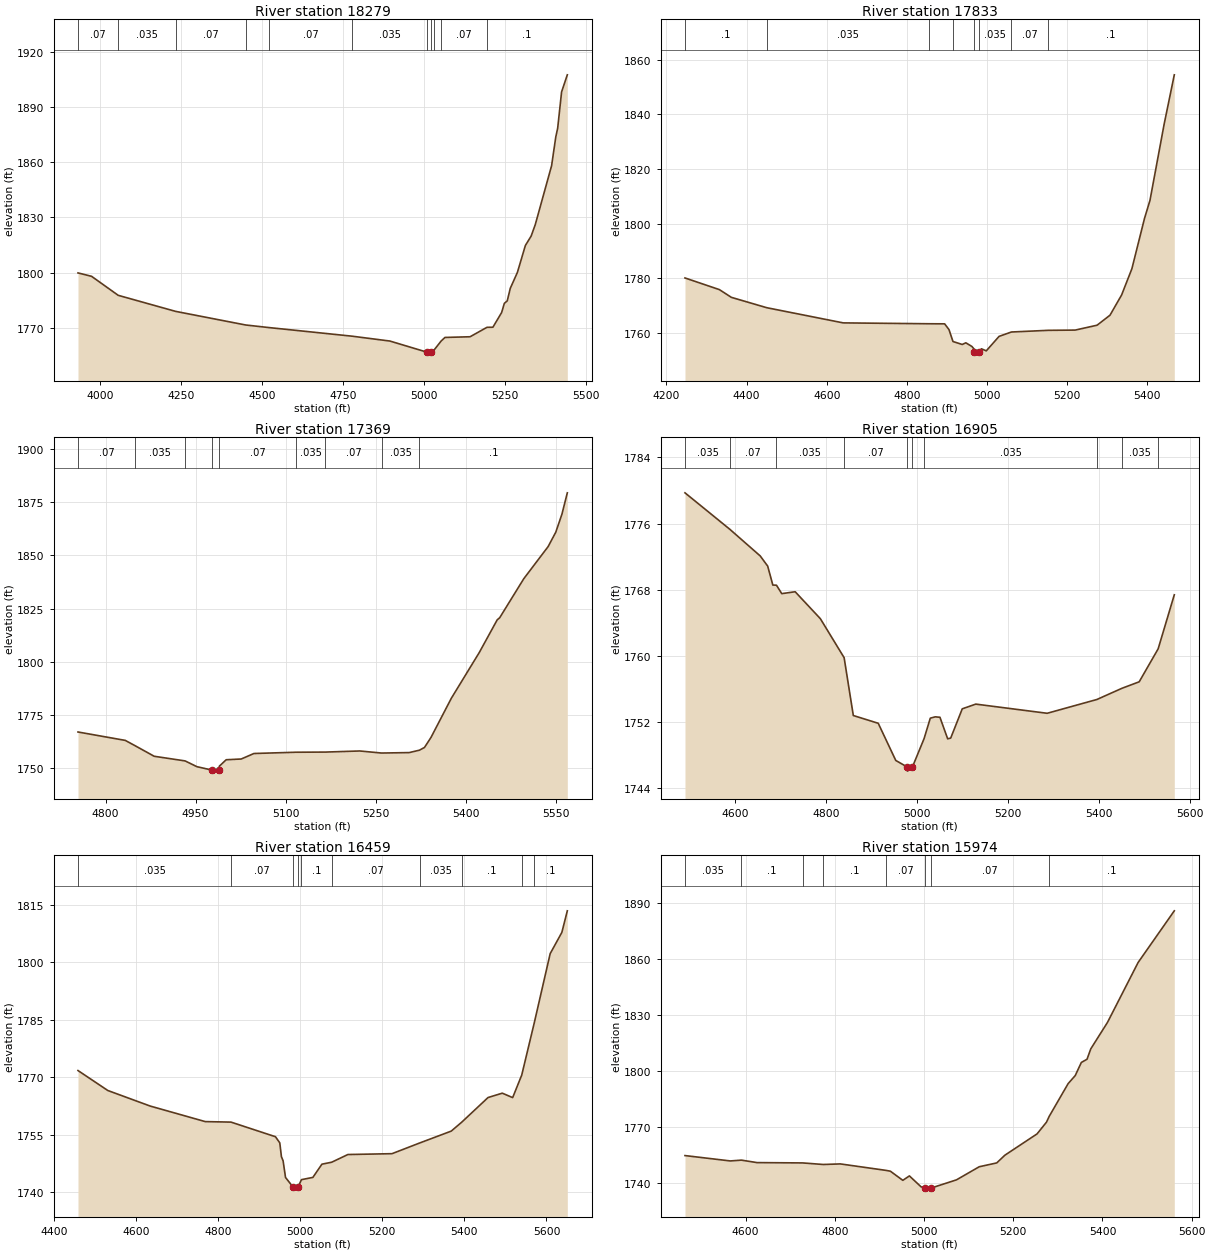
Type RM Length L Ch R = 1 ,18279   ,446,446,446
BEGIN DESCRIPTION:
Bear Creek 38.0
END DESCRIPTION:
XS GIS Cut Line= 3
      1896274.97     13926524.98        1897075.       13927225.
      1897475.03     13927425.02
#Sta/Elev= 30
    3933 1799.86    3975    1798  4057.1 1787.69  4234.2 1778.98  4450.3 1771.59
    4522 1770.19  4778.9 1765.51  4895.9 1762.86  5010.4 1756.81  5010.9 1756.31
  5021.1 1756.81  5031.9 1757.96  5053.4  1762.8  5065.6 1764.82  5143.2  1765.2
  5195.3 1770.32  5213.6 1770.37  5240.5 1778.34  5248.9 1783.33  5257.9 1784.69
  5267.3 1791.51  5289.2 1800.13  5313.8 1814.73  5331.7 1819.88  5344.4 1826.09
  5394.8 1858.09  5407.7 1873.69  5413.5 1878.39  5425.6 1898.12  5443.3  1907.4
#Mann= 11 ,-1 , 0
    3933     .07       0  4057.1    .035       0  4234.2     .07       0
  4450.3    .035       0    4522     .07       0  4778.9    .035       0
  5010.4    .035       0  5021.1    .035       0  5031.9      .1       0
  5053.4     .07       0  5195.3      .1       0
Bank Sta=5010.4,5021.1
XS Rating Curve= 0 ,0
Exp/Cntr=0.3,0.1

Type RM Length L Ch R = 1 ,17833   ,464,464,464
BEGIN DESCRIPTION:
Bear Creek 37.0
END DESCRIPTION:
XS GIS Cut Line= 3
      1896220.81     13927598.64      1896975.09     13927606.79
      1897410.21     13927438.11
#Sta/Elev= 30
  4246.4 1780.05  4332.2 1775.78  4362.2 1772.94  4450.5 1769.15  4641.2 1763.59
  4854.7 1763.27  4894.3 1763.24  4905.2 1761.13  4915.1 1756.77  4938.2 1755.68
  4947.2 1756.29  4962.2 1754.97  4968.2 1753.93  4968.8 1753.01  4969.3 1752.51
  4979.7 1753.01  4986.2 1754.09  4998.2 1753.34  5030.2 1758.65    5061 1760.25
  5152.5 1760.86  5220.1 1760.95  5274.7 1762.74    5307 1766.41  5335.9 1773.81
  5361.6 1783.44  5393.1 1801.89  5406.7 1808.47  5442.1 1836.42  5467.4 1854.47
#Mann= 8 ,-1 , 0
  4246.4      .1       0  4450.5    .035       0  4854.7     .07       0
  4915.1    .035       0  4968.8    .035       0  4979.7    .035       0
    5061     .07       0  5152.5      .1       0
Bank Sta=4968.8,4979.7
XS Rating Curve= 0 ,0
Exp/Cntr=0.3,0.1

Type RM Length L Ch R = 1 ,17369   ,464,464,464
BEGIN DESCRIPTION:
Bear Creek 36.0
END DESCRIPTION:
XS GIS Cut Line= 3
      1896925.03     13928124.97        1897125.       13927975.
      1897524.97     13927575.03
#Sta/Elev= 30
  4754.1 1767.06  4832.9 1763.11  4849.6 1760.56  4881.1 1755.65  4932.6 1753.47
  4952.3 1750.76  4977.2 1749.17  4977.7 1748.67  4988.6 1749.17  4989.8 1751.03
  5001.1 1754.02  5026.1 1754.36  5047.3 1756.95  5117.6 1757.55  5166.1 1757.62
  5223.7 1758.14    5260 1757.17  5306.1 1757.38  5323.2 1758.51  5331.6 1759.79
  5342.5 1764.52  5376.4 1782.92  5423.1 1804.48  5452.8 1819.75    5457 1820.77
  5497.1 1839.08  5537.7 1854.18  5550.4 1860.92  5560.7 1869.39  5569.7 1879.45
#Mann= 9 ,-1 , 0
  4754.1     .07       0  4849.6    .035       0  4932.6     .07       0
  4977.2     .05       0  4988.6     .07       0  5117.6    .035       0
  5166.1     .07       0    5260    .035       0  5323.2      .1       0
Bank Sta=4977.2,4988.6
XS Rating Curve= 0 ,0
Exp/Cntr=0.3,0.1

Type RM Length L Ch R = 1 ,16905   ,446,446,446
BEGIN DESCRIPTION:
Bear Creek 35.0
END DESCRIPTION:
XS GIS Cut Line= 3
      1896978.13     13928645.91        1897375.       13928325.
      1897775.02     13927924.98
#Sta/Elev= 30
  4489.6 1779.72  4588.4  1775.3  4655.1 1772.08  4671.5 1770.85  4682.8 1768.56
  4690.8 1768.54  4702.4 1767.52  4731.9 1767.75  4787.3 1764.49  4839.6 1759.77
  4859.8 1752.77  4914.6 1751.83  4953.2 1747.33  4978.4 1746.54  4978.9 1746.04
  4989.8 1746.54  5015.4 1749.97  5029.1 1752.45    5040 1752.61  5050.3 1752.56
  5067.3 1749.95    5074 1750.04  5099.4 1753.58  5129.1 1754.15  5286.1 1753.04
  5395.5 1754.71  5450.4 1756.06  5488.5 1756.85  5530.2 1760.84  5565.7 1767.38
#Mann= 10 ,-1 , 0
  4489.6    .035       0  4588.4     .07       0  4690.8    .035       0
  4839.6     .07       0  4978.4     .05       0  4989.8     .07       0
  5015.4    .035       0  5395.5     .07       0  5450.4    .035       0
  5530.2      .1       0
Bank Sta=4978.4,4989.8
XS Rating Curve= 0 ,0
Exp/Cntr=0.3,0.1

Type RM Length L Ch R = 1 ,16459   ,485,485,485
BEGIN DESCRIPTION:
Bear Creek 34.0
END DESCRIPTION:
XS GIS Cut Line= 3
      1897447.69     13928890.09        1897725.       13928425.
      1897931.16     13927807.38
#Sta/Elev= 30
  4458.2 1771.73  4530.8 1766.52  4634.2 1762.45  4768.4 1758.39  4831.1 1758.26
  4939.5 1754.44    4950 1752.83    4954 1749.23  4958.1 1748.13    4964 1743.79
  4982.7 1741.25  4983.2 1740.75  4994.2 1741.25  5002.9 1743.23  5030.6 1743.81
  5052.7 1747.27  5076.5 1747.78    5116 1749.79  5223.5 1750.01  5290.8  1752.8
  5367.9 1755.91  5393.3 1758.23  5457.6 1764.68  5492.3 1765.82  5517.6 1764.66
  5539.7 1770.55  5569.9 1784.04    5609 1802.27  5637.5 1807.83  5650.8 1813.46
#Mann= 10 ,-1 , 0
  4458.2    .035       0  4831.1     .07       0  4982.7     .05       0
  4994.2     .07       0  5002.9      .1       0  5076.5     .07       0
  5290.8    .035       0  5393.3      .1       0  5539.7     .07       0
  5569.9      .1       0
Bank Sta=4982.7,4994.2
XS Rating Curve= 0 ,0
Exp/Cntr=0.3,0.1

Type RM Length L Ch R = 1 ,15974   ,447,447,447
BEGIN DESCRIPTION:
Bear Creek 33.0
END DESCRIPTION:
XS GIS Cut Line= 3
      1897774.97     13928775.03        1898175.       13928425.
      1898574.97     13928025.03
#Sta/Elev= 30
  4463.9 1754.66  4565.7 1751.78  4590.4 1752.22  4625.5 1750.89  4727.6 1750.72
  4774.1 1749.88  4812.2 1750.19  4914.4 1746.73  4924.5 1746.28  4952.4 1741.38
  4967.1 1743.76  4993.3 1737.91  5003.2 1737.17  5003.7 1736.67  5014.8 1737.17
  5072.7 1741.64  5123.6 1748.66    5163 1750.73  5181.2 1754.86  5253.3 1766.27
  5274.5 1772.57  5280.6 1775.68    5323 1793.22    5339 1797.57  5352.7  1804.6
  5365.4 1806.31  5373.9 1811.91  5411.2 1826.03    5480  1858.2  5561.1 1885.89
#Mann= 8 ,-1 , 0
  4463.9    .035       0  4590.4      .1       0  4727.6     .07       0
  4774.1      .1       0  4914.4     .07       0  5003.2     .05       0
  5014.8     .07       0  5280.6      .1       0
Bank Sta=5003.2,5014.8
XS Rating Curve= 0 ,0
Exp/Cntr=0.3,0.1

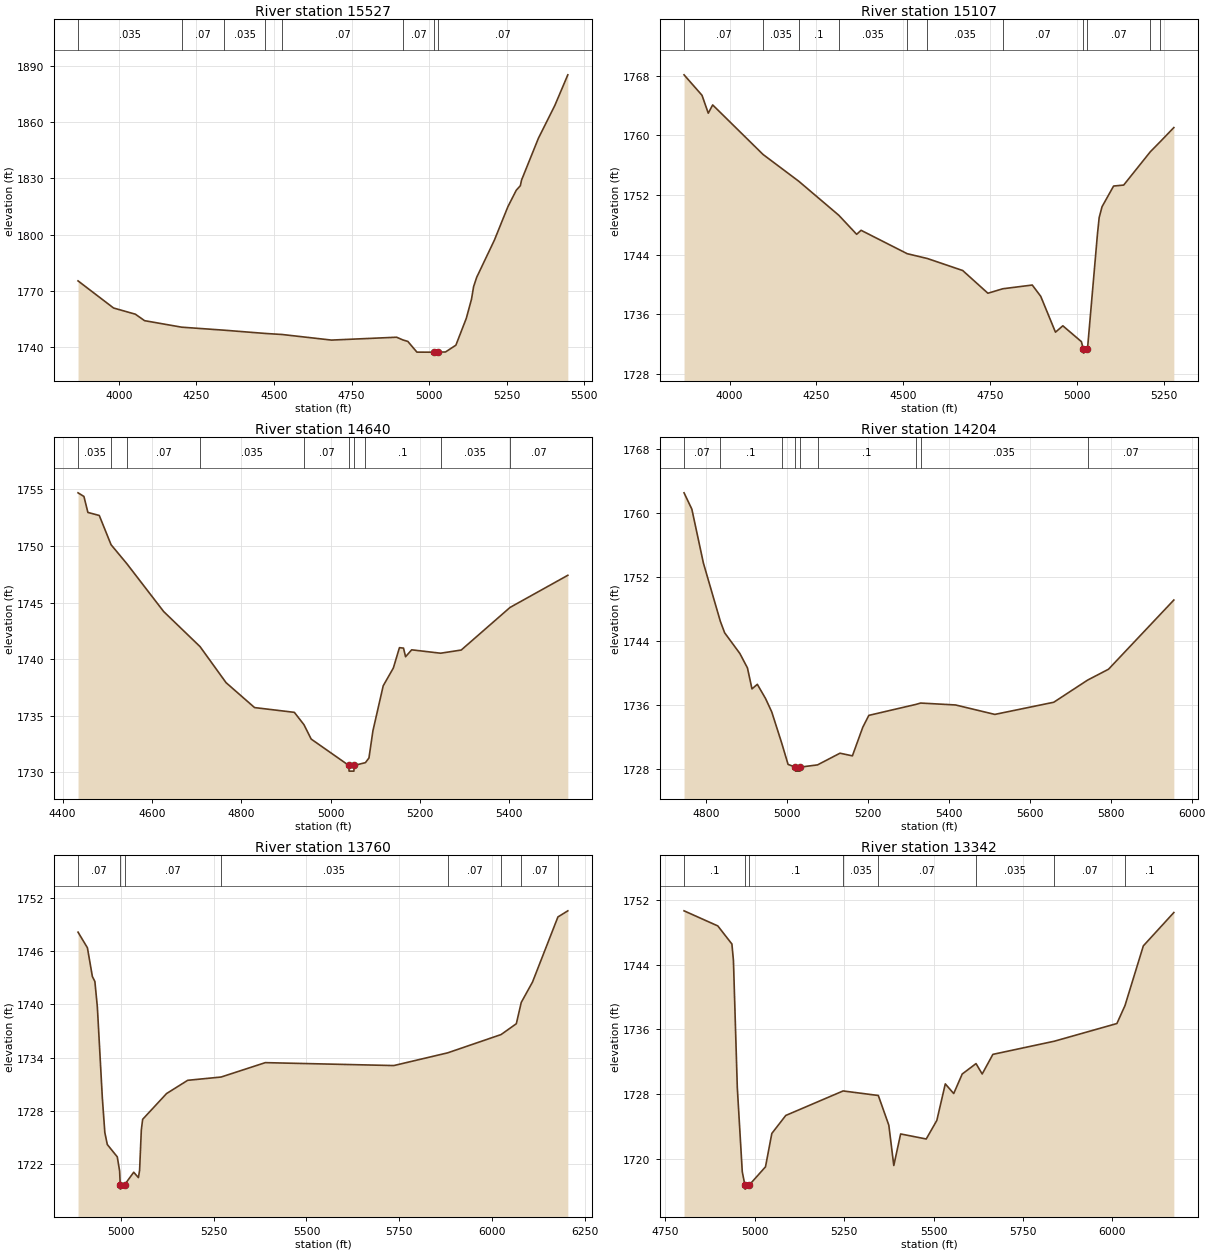
Type RM Length L Ch R = 1 ,15527   ,420,420,420
BEGIN DESCRIPTION:
Bear Creek 32.0
END DESCRIPTION:
XS GIS Cut Line= 3
      1897774.97     13929375.03        1898575.       13928575.
      1898774.99     13928175.02
#Sta/Elev= 30
  3868.6  1775.2  3983.1 1760.68  4053.4 1757.37  4083.1  1753.9  4202.9 1750.41
  4337.7 1748.83  4472.5 1747.06  4526.9 1746.49  4685.5 1743.51  4895.3 1745.04
  4915.5  1743.6  4931.4 1742.81  4960.9 1737.06  5016.9 1737.03  5017.4 1736.53
  5028.5 1737.03    5053 1737.15  5086.4 1740.78    5120 1755.16  5136.8 1765.44
  5143.5 1772.09  5153.5 1777.12  5210.5    1797  5254.2 1814.96    5281 1823.71
  5294.3 1826.17  5297.8 1829.05  5352.5 1851.57  5405.1    1869  5447.2 1885.48
#Mann= 8 ,-1 , 0
  3868.6    .035       0  4202.9     .07       0  4337.7    .035       0
  4472.5      .1       0  4526.9     .07       0  4915.5     .07       0
  5016.9     .05       0  5028.5     .07       0
Bank Sta=5016.9,5028.5
XS Rating Curve= 0 ,0
Exp/Cntr=0.3,0.1

Type RM Length L Ch R = 1 ,15107   ,467,467,467
BEGIN DESCRIPTION:
Bear Creek 31.0
END DESCRIPTION:
XS GIS Cut Line= 3
      1898024.97     13929675.03        1898825.       13928875.
      1899026.97     13928681.54
#Sta/Elev= 30
  3868.6 1768.13  3920.4 1765.38  3938.4 1762.98  3951.1 1764.09  4096.2 1757.44
  4198.7 1753.86  4314.4 1749.28  4365.9 1746.72  4378.6 1747.26  4511.4 1744.12
  4569.7 1743.47  4671.4 1741.86    4744 1738.81  4786.9 1739.41  4871.8 1739.91
  4896.2  1738.4  4938.7 1733.58  4959.9 1734.44  5013.4 1732.31  5019.2 1731.27
  5019.7 1730.77  5030.8 1731.27  5059.7 1746.79  5064.6 1748.97  5072.8 1750.42
  5106.1  1753.2  5135.2 1753.33  5211.7 1757.79  5240.2 1759.14  5279.7 1761.05
#Mann= 11 ,-1 , 0
  3868.6     .07       0  4096.2    .035       0  4198.7      .1       0
  4314.4    .035       0  4511.4      .1       0  4569.7    .035       0
  4786.9     .07       0  5019.2     .05       0  5030.8     .07       0
  5211.7     .07       0  5240.2      .1       0
Bank Sta=5019.2,5030.8
XS Rating Curve= 0 ,0
Exp/Cntr=0.3,0.1

Type RM Length L Ch R = 1 ,14640   ,436,436,436
BEGIN DESCRIPTION:
Bear Creek 30.0
END DESCRIPTION:
XS GIS Cut Line= 3
      1898474.97     13929725.03        1898875.       13929325.
      1899224.98     13928925.02
#Sta/Elev= 30
  4434.4 1754.69  4447.6 1754.37  4456.5 1752.96    4482 1752.69  4508.4 1750.11
  4543.8 1748.43  4626.2 1744.21  4707.8 1741.11    4766 1737.93  4829.9 1735.73
    4919 1735.31  4940.5 1734.22  4956.7 1732.95  5041.1 1730.62  5041.6 1730.12
  5052.4 1730.12  5052.9 1730.62  5078.2 1730.87  5086.1 1731.28    5095 1733.68
    5118 1737.65  5140.8 1739.23  5154.4 1741.02  5163.5 1740.98  5168.1 1740.22
  5181.8 1740.83  5246.6 1740.53  5292.8 1740.81  5402.1 1744.57  5531.6 1747.41
#Mann= 10 ,-1 , 0
  4434.4    .035       0  4508.4      .1       0  4543.8     .07       0
  4707.8    .035       0  4940.5     .07       0  5041.1     .05       0
  5052.9     .07       0  5078.2      .1       0  5246.6    .035       0
  5402.1     .07       0
Bank Sta=5041.1,5052.9
XS Rating Curve= 0 ,0
Exp/Cntr=0.3,0.1

Type RM Length L Ch R = 1 ,14204   ,444,444,444
BEGIN DESCRIPTION:
Bear Creek 29.0
END DESCRIPTION:
XS GIS Cut Line= 4
      1898774.98     13929925.03        1898925.       13929725.
      1899226.97     13929322.38      1899281.38     13928868.45
#Sta/Elev= 30
  4745.5 1762.57  4764.8 1760.53  4793.4 1753.78  4835.2 1746.51  4845.9 1745.07
  4883.4 1742.49  4902.2 1740.68  4913.4 1738.06  4926.6 1738.63  4946.9 1736.86
  4962.2 1735.19  4986.8  1731.3  5002.6 1728.62  5020.6 1728.28  5021.1 1727.78
    5032 1727.78  5032.5 1728.28  5075.4 1728.56  5130.9 1730.02  5161.6 1729.69
  5187.2 1733.26  5202.2 1734.75  5319.3 1736.13  5330.1 1736.29  5416.6 1736.05
  5513.6 1734.87  5659.2 1736.39  5742.9 1739.16  5794.6 1740.52    5956 1749.17
#Mann= 9 ,-1 , 0
  4745.5     .07       0  4835.2      .1       0  4986.8     .07       0
  5020.6     .05       0  5032.5     .07       0  5075.4      .1       0
  5319.3     .07       0  5330.1    .035       0  5742.9     .07       0
Bank Sta=5020.6,5032.5
XS Rating Curve= 0 ,0
Exp/Cntr=0.3,0.1

Type RM Length L Ch R = 1 ,13760   ,418,418,418
BEGIN DESCRIPTION:
Bear Creek 28.0
END DESCRIPTION:
XS GIS Cut Line= 4
      1899125.01       13930075.        1899225.       13930025.
      1899513.54     13929159.93      1899494.67     13928864.35
#Sta/Elev= 30
  4884.4 1748.12  4909.7 1746.36  4923.1 1743.12  4929.8 1742.57  4936.5 1739.69
  4949.9 1729.47  4956.6 1725.57  4963.3 1724.21  4990.2 1722.82  4996.5 1721.23
  4998.1 1719.69  4998.6 1719.19    5010 1719.69  5034.5 1721.09  5047.1 1720.49
  5050.3  1721.3    5055 1725.87  5058.6 1727.05    5123 1729.95  5179.9 1731.44
    5270 1731.81  5389.1 1733.43  5735.3  1733.1  5880.3 1734.53  6024.4 1736.59
  6065.5 1737.81  6078.8 1740.21  6109.1  1742.5  6177.6 1749.83  6204.3 1750.52
#Mann= 8 ,-1 , 0
  4884.4     .07       0  4998.1     .05       0    5010     .07       0
    5270    .035       0  5880.3     .07       0  6024.4    .035       0
  6078.8     .07       0  6177.6      .1       0
Bank Sta=4998.1,5010
XS Rating Curve= 0 ,0
Exp/Cntr=0.3,0.1

Type RM Length L Ch R = 1 ,13342   ,357,357,357
BEGIN DESCRIPTION:
Bear Creek 27.0
END DESCRIPTION:
XS GIS Cut Line= 4
      1899547.27      13930221.3        1899575.       13930025.
       1899562.8     13929191.39      1899541.43     13928854.71
#Sta/Elev= 30
  4802.2 1750.62  4896.6 1748.76    4936 1746.53  4940.3 1744.49  4951.1 1728.83
    4965 1718.46  4972.3 1716.82  4972.8 1716.32  4984.4 1716.82  5029.9 1719.07
  5047.6 1723.18  5086.6  1725.4  5246.9 1728.42  5345.3 1727.86  5374.7  1724.2
  5388.6 1719.23  5407.7 1723.12  5479.3  1722.5  5508.9 1724.79  5532.6 1729.29
  5556.1  1728.1  5579.9 1730.51  5618.5 1731.79  5635.7 1730.51  5665.6 1732.93
  5837.4 1734.55  6012.3 1736.73  6034.9 1738.94  6086.2  1746.3  6171.5 1750.41
#Mann= 8 ,-1 , 0
  4802.2      .1       0  4972.3     .05       0  4984.4      .1       0
  5246.9    .035       0  5345.3     .07       0  5618.5    .035       0
  5837.4     .07       0  6034.9      .1       0
Bank Sta=4972.3,4984.4
XS Rating Curve= 0 ,0
Exp/Cntr=0.3,0.1

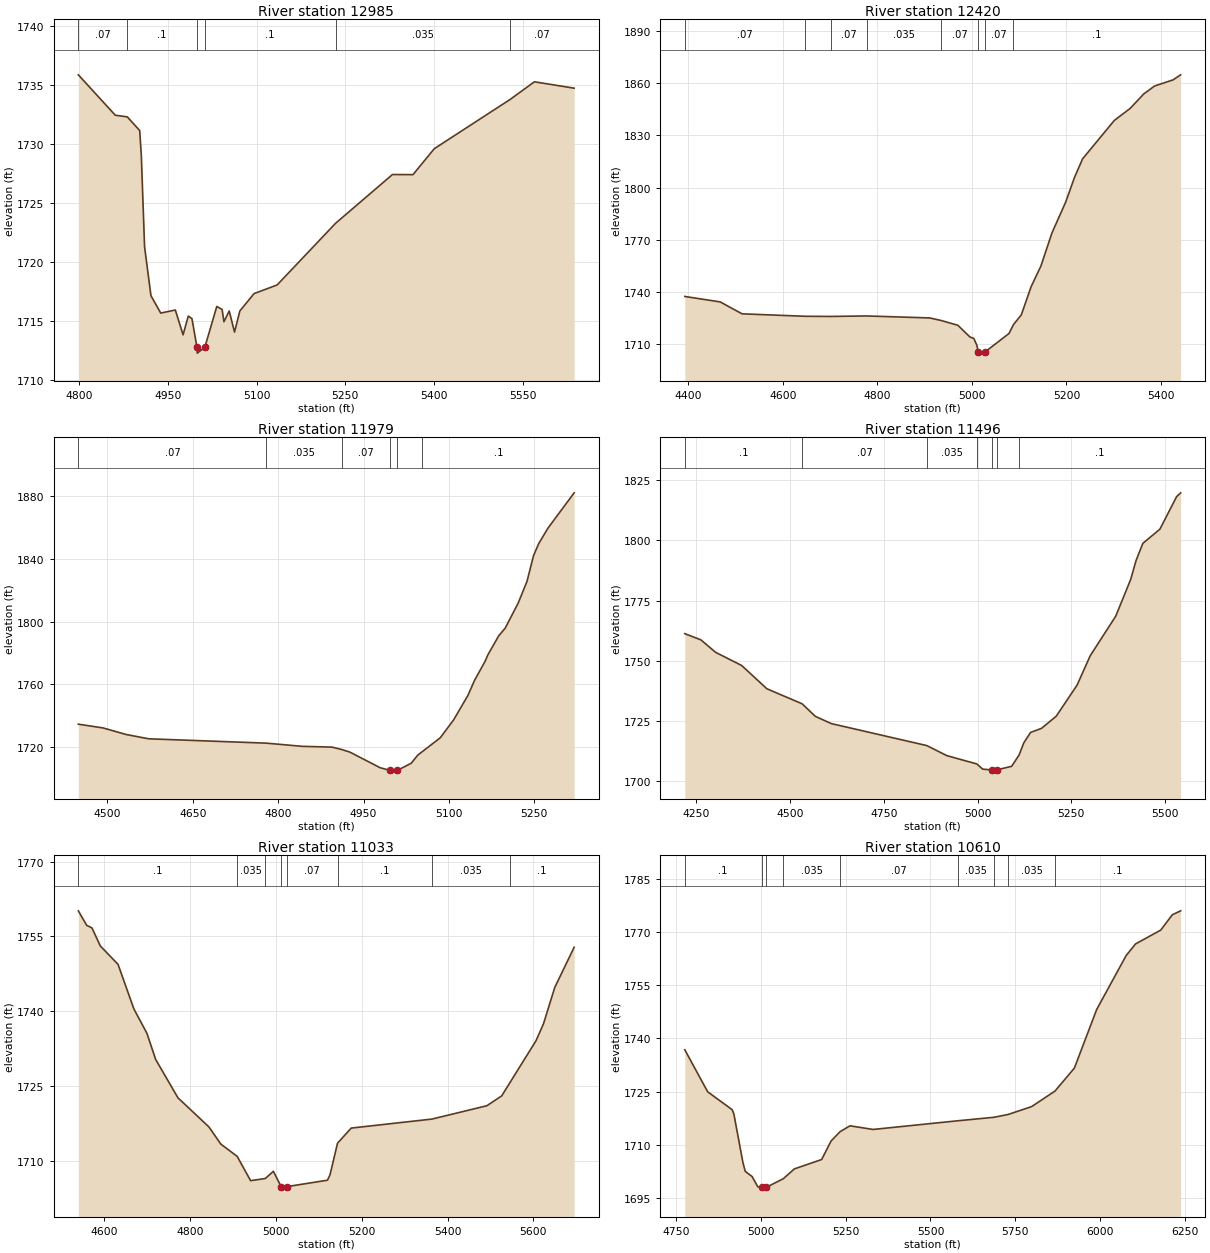
Type RM Length L Ch R = 1 ,12985   ,565,565,565
BEGIN DESCRIPTION:
Bear Creek 26.0
END DESCRIPTION:
XS GIS Cut Line= 3
        1899875.     13930024.97      1899856.07     13929840.46
      1899859.32     13929187.64
#Sta/Elev= 30
  4798.6 1735.84  4861.1 1732.42  4881.4 1732.28  4902.4 1731.12  4905.1 1729.03
  4910.6 1721.28  4921.4 1717.14  4937.9 1715.67  4962.6 1715.93  4975.7 1713.83
  4984.5 1715.42  4990.7  1715.2  4999.2 1712.78  4999.7 1712.28  5012.5 1712.78
  5032.7 1716.23  5041.7 1715.98  5044.8 1714.94  5053.7 1715.85  5062.7 1714.06
  5071.7 1715.85  5095.7 1717.32  5134.7 1718.05  5233.5 1723.27  5329.7  1727.4
  5364.4 1727.39  5400.5 1729.59  5528.5 1733.75  5569.7 1735.25  5636.9 1734.71
#Mann= 6 ,-1 , 0
  4798.6     .07       0  4881.4      .1       0  4999.2     .05       0
  5012.5      .1       0  5233.5    .035       0  5528.5     .07       0
Bank Sta=4999.2,5012.5
XS Rating Curve= 0 ,0
Exp/Cntr=0.3,0.1

Type RM Length L Ch R = 1 ,12420   ,441,441,441
BEGIN DESCRIPTION:
Bear Creek 25.0
END DESCRIPTION:
XS GIS Cut Line= 3
        1899912.      13930103.4        1900275.       13929625.
      1900690.22     13929454.49
#Sta/Elev= 30
  4392.4 1737.28  4467.2 1734.15  4513.7 1727.28  4647.2 1725.87  4701.3 1725.78
  4777.2 1726.06  4910.7 1724.92  4935.4 1723.42  4970.3  1720.7    4996 1713.93
  5004.1 1713.12  5010.6 1709.18  5013.6 1705.16  5014.1 1704.66    5027 1705.16
  5078.7    1716    5088 1721.07  5104.6 1726.66  5125.3 1742.85  5146.1  1754.8
  5169.5 1773.87  5198.7  1791.7  5217.1 1805.75  5234.3 1816.49  5301.3 1838.57
  5334.9 1845.52  5364.1 1853.95  5386.8 1858.45  5425.7 1861.94  5441.8 1864.87
#Mann= 8 ,-1 , 0
  4392.4     .07       0  4647.2      .1       0  4701.3     .07       0
  4777.2    .035       0  4935.4     .07       0  5013.6     .05       0
    5027     .07       0    5088      .1       0
Bank Sta=5013.6,5027
XS Rating Curve= 0 ,0
Exp/Cntr=0.3,0.1

Type RM Length L Ch R = 1 ,11979   ,483,483,483
BEGIN DESCRIPTION:
Bear Creek 24.0
END DESCRIPTION:
XS GIS Cut Line= 3
      1899979.07     13930215.58        1900475.       13929975.
      1900725.03     13929774.97
#Sta/Elev= 30
  4448.8 1734.36  4492.4 1731.95  4532.4 1727.79  4572.4 1725.01  4779.2 1722.23
  4842.5 1720.18  4894.5  1719.7  4911.6 1718.17  4925.9 1716.52  4979.2 1706.52
  4996.3 1704.84  4996.8 1704.34  5009.7 1704.84  5033.9 1709.41  5045.2 1714.52
  5053.5 1716.86    5085 1725.69  5108.5 1737.18  5133.6 1752.82  5145.1 1762.36
  5163.6  1774.5  5168.4 1778.56  5187.6 1790.84  5198.9 1795.69  5221.9 1811.84
  5237.3 1825.63  5248.8  1842.1  5257.9  1849.8    5274 1859.61  5320.2 1882.28
#Mann= 6 ,-1 , 0
  4448.8     .07       0  4779.2    .035       0  4911.6     .07       0
  4996.3     .05       0  5009.7     .07       0  5053.5      .1       0
Bank Sta=4996.3,5009.7
XS Rating Curve= 0 ,0
Exp/Cntr=0.3,0.1

Type RM Length L Ch R = 1 ,11496   ,463,463,463
BEGIN DESCRIPTION:
Bear Creek 23.0
END DESCRIPTION:
XS GIS Cut Line= 3
        1900075.       13931025.        1900575.       13930425.
      1900875.03     13929974.96
#Sta/Elev= 30
  4219.6 1761.27  4262.5 1758.69  4301.8 1753.51  4371.2 1748.07  4438.5  1738.4
  4532.5 1732.17  4567.4 1726.99  4610.3 1723.96  4864.9 1714.84  4918.3 1710.67
  4998.1 1707.23  5013.8 1705.08  5037.3 1704.75  5037.8 1704.25  5050.8 1704.75
    5091 1706.25  5110.9 1710.96  5123.4 1715.98  5141.4 1720.29  5170.6 1721.98
  5209.9 1727.03  5265.6 1739.96  5300.4 1752.08  5368.6 1768.54  5408.3 1783.73
  5422.7  1791.6  5440.7 1798.69  5486.3 1804.61  5530.8 1818.09  5541.5 1819.67
#Mann= 7 ,-1 , 0
  4219.6      .1       0  4532.5     .07       0  4864.9    .035       0
  4998.1     .07       0  5037.3     .05       0  5050.8     .07       0
  5110.9      .1       0
Bank Sta=5037.3,5050.8
XS Rating Curve= 0 ,0
Exp/Cntr=0.3,0.1

Type RM Length L Ch R = 1 ,11033   ,423,423,423
BEGIN DESCRIPTION:
Bear Creek 22.0
END DESCRIPTION:
XS GIS Cut Line= 3
      1900375.02     13931174.98        1900675.       13930825.
      1901025.01     13930224.98
#Sta/Elev= 30
  4539.4 1760.11  4558.9  1757.2  4571.2 1756.68  4590.6 1753.07    4632 1749.36
  4668.9 1740.42  4699.3 1735.53  4719.6 1730.29  4771.6 1722.58  4843.8 1716.74
  4871.5  1713.3  4909.7 1710.83  4940.9 1705.96  4975.1 1706.39    4994 1707.84
  5012.1 1704.76  5012.6 1704.26  5025.6 1704.76    5120 1706.05    5126 1707.14
  5143.5 1713.48  5175.4 1716.51  5363.7 1718.32  5491.4 1720.99  5526.1 1722.97
  5544.5 1725.51    5606 1734.03  5623.4 1737.41  5649.9 1744.75    5695  1752.8
#Mann= 8 ,-1 , 0
  4539.4      .1       0  4909.7    .035       0  4975.1     .07       0
  5012.1     .05       0  5025.6     .07       0  5143.5      .1       0
  5363.7    .035       0  5544.5      .1       0
Bank Sta=5012.1,5025.6
XS Rating Curve= 0 ,0
Exp/Cntr=0.3,0.1

Type RM Length L Ch R = 1 ,10610   ,444,444,444
BEGIN DESCRIPTION:
Bear Creek 21.0
END DESCRIPTION:
XS GIS Cut Line= 3
      1900675.02     13931274.99        1900875.       13931175.
        1901175.     13929975.02
#Sta/Elev= 30
  4776.4 1736.79  4843.8 1724.92  4916.1 1719.86    4921 1718.63  4947.8 1704.86
  4954.5 1702.45  4974.6    1701  4991.4 1698.12  5002.7 1697.94  5003.2 1697.44
  5016.2 1697.94  5066.4 1700.37  5099.1 1703.15  5179.5  1705.8  5207.3 1711.03
  5233.6 1713.65    5263 1715.32    5331 1714.29  5580.8 1716.74  5687.7 1717.73
  5729.2 1718.53    5798 1720.74  5866.8 1725.12    5924 1731.62  5989.7 1748.17
  6076.3 1763.37  6104.1 1766.67  6178.3 1770.58  6212.4  1774.9  6236.9 1776.02
#Mann= 9 ,-1 , 0
  4776.4      .1       0  5002.7     .05       0  5016.2      .1       0
  5066.4    .035       0  5233.6     .07       0  5580.8    .035       0
  5687.7     .07       0  5729.2    .035       0  5866.8      .1       0
Bank Sta=5002.7,5016.2
XS Rating Curve= 0 ,0
Exp/Cntr=0.3,0.1

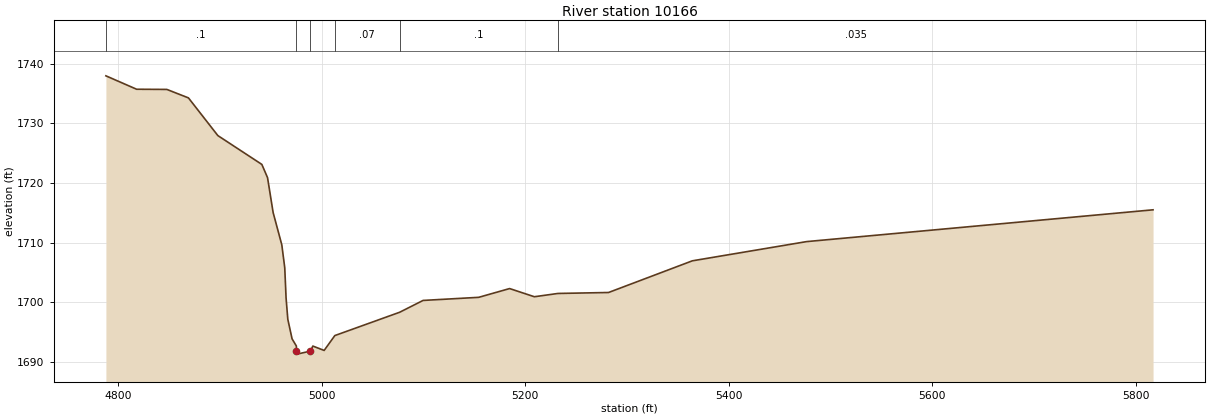
Type RM Length L Ch R = 1 ,10166   ,929,929,929
BEGIN DESCRIPTION:
Bear Creek 20.0
END DESCRIPTION:
XS GIS Cut Line= 3
      1900974.98     13931675.02        1901125.       13931525.
      1901253.58     13930718.65
#Sta/Elev= 30
  4788.2 1737.98  4818.4 1735.73  4848.1  1735.7  4869.3 1734.28  4898.2 1727.96
  4941.4 1723.13    4947 1720.91  4952.5 1715.05    4961 1709.66  4963.9 1705.82
  4965.2 1700.75  4966.9 1697.18  4971.1 1693.89  4975.3 1692.69  4975.4 1691.83
  4975.9 1691.33  4989.1 1691.83  4991.5 1692.68  5002.6 1691.95  5013.1 1694.44
  5076.8 1698.35  5099.8 1700.33  5154.4 1700.85  5184.8 1702.32  5209.1 1700.95
  5232.3  1701.5    5282 1701.66  5364.3 1706.97  5476.5 1710.19  5816.9 1715.52
#Mann= 6 ,-1 , 0
  4788.2      .1       0  4975.4     .05       0  4989.1      .1       0
  5013.1     .07       0  5076.8      .1       0  5232.3    .035       0
Bank Sta=4975.4,4989.1
XS Rating Curve= 0 ,0
Exp/Cntr=0.3,0.1