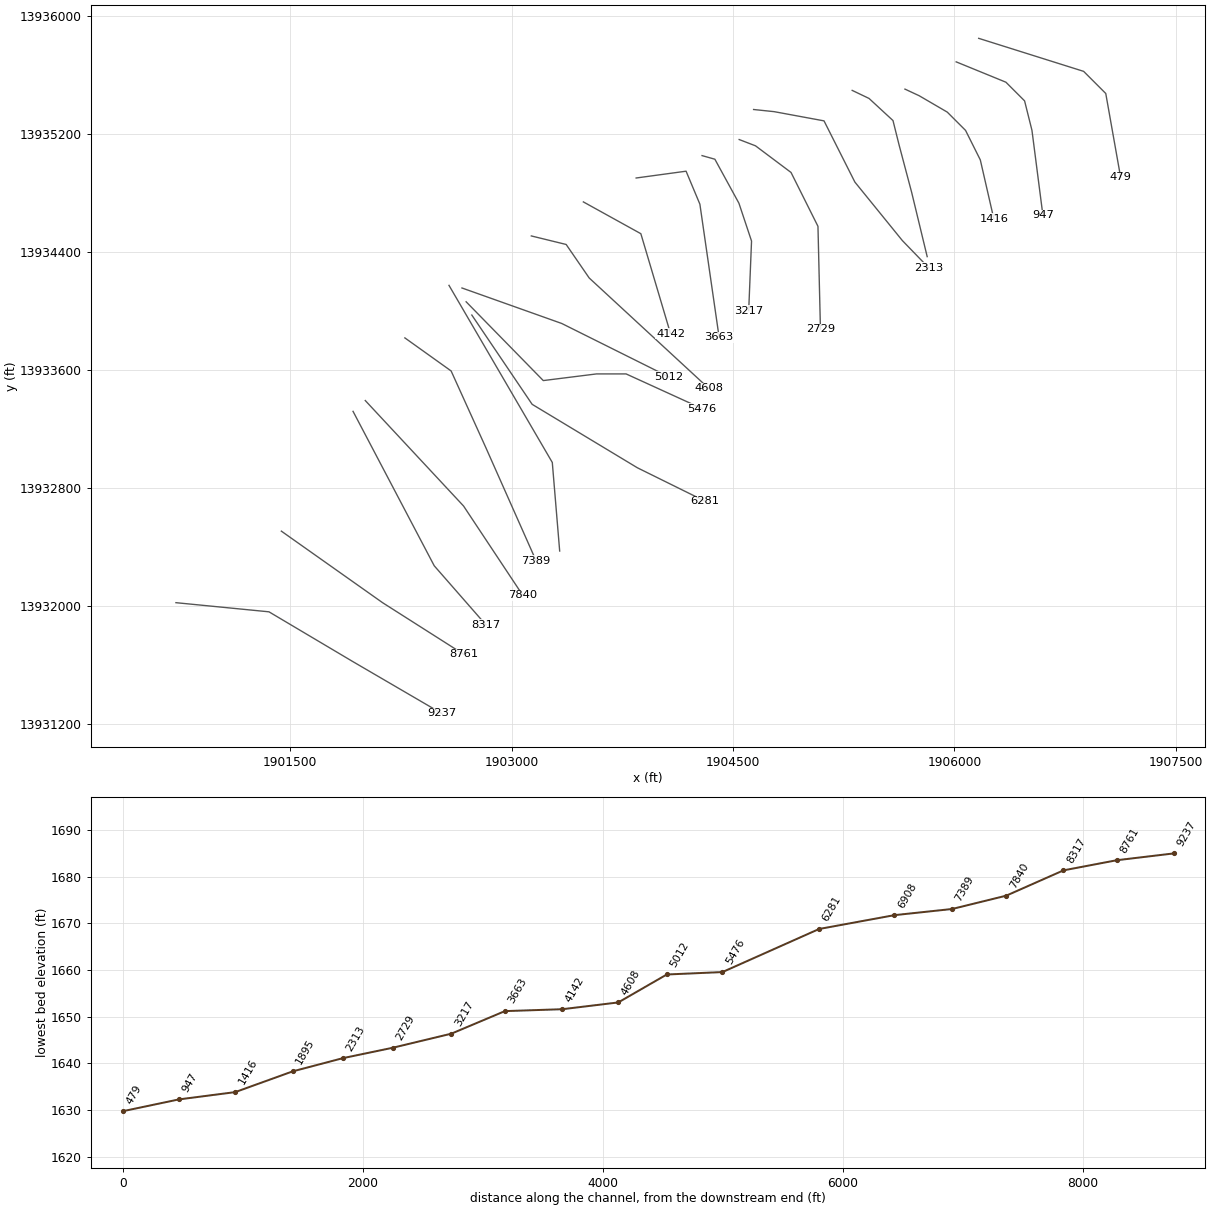
HEC-RAS study Bear Creek.prj: Bear Creek_US Base Level Engineering

--- Bear Creek.g01 (geometry) --- (continued)

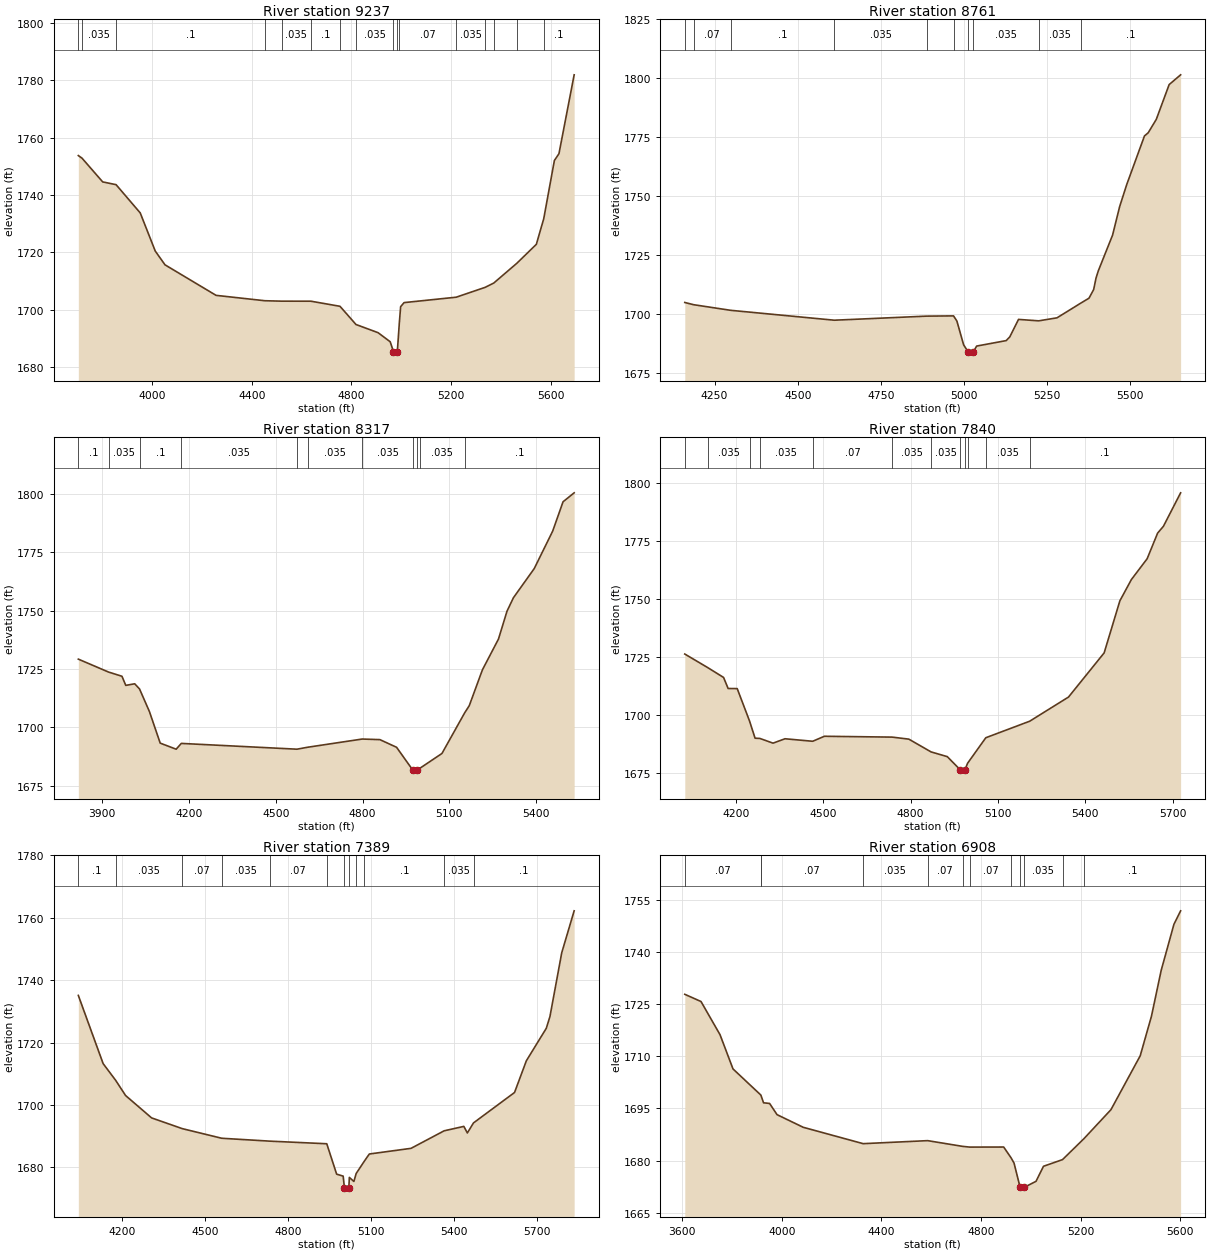
Type RM Length L Ch R = 1 ,9237    ,476,476,476
BEGIN DESCRIPTION:
Bear Creek 19.0
END DESCRIPTION:
XS GIS Cut Line= 4
      1900724.96       13932025.      1901355.26     13931963.08
        1901925.       13931625.      1902525.04     13931274.98
#Sta/Elev= 30
  3703.7 1753.71  3718.4 1752.82  3801.5 1744.55  3855.2 1743.59  3952.2 1733.76
  4012.5 1720.49  4051.6  1715.7  4256.7 1705.07  4452.6  1703.2  4520.4 1703.05
  4637.3 1703.04  4754.2 1701.26  4818.4 1694.93  4906.9 1692.09  4955.7 1688.93
  4968.9 1685.47  4969.4 1684.97  4984.3 1685.47  4992.4  1695.5  4997.6 1701.13
  5011.5 1702.55  5220.6 1704.43  5336.9 1707.86  5371.4 1709.35  5463.4 1716.18
  5542.4 1722.83  5572.1 1731.74  5614.8 1751.99  5633.2 1754.37  5694.2 1781.81
#Mann= 16 ,-1 , 0
  3703.7      .1       0  3718.4    .035       0  3855.2      .1       0
  4452.6     .07       0  4520.4    .035       0  4637.3      .1       0
  4754.2    .035       0  4818.4    .035       0  4968.9    .035       0
  4984.3    .035       0  4992.4     .07       0  5220.6    .035       0
  5336.9     .07       0  5371.4      .1       0  5463.4     .07       0
  5572.1      .1       0
Bank Sta=4968.9,4984.3
XS Rating Curve= 0 ,0
Exp/Cntr=0.3,0.1

Type RM Length L Ch R = 1 ,8761    ,444,444,444
BEGIN DESCRIPTION:
Bear Creek 18.0
END DESCRIPTION:
XS GIS Cut Line= 3
      1901439.26     13932509.67        1902125.       13932025.
      1902675.04     13931674.97
#Sta/Elev= 30
  4160.3 1704.99  4186.7 1704.05  4297.9 1701.67  4610.3 1697.47  4887.6  1699.2
  4968.8  1699.3  4978.9 1697.12  4999.2 1687.02  5012.8 1684.01  5013.3 1683.51
  5028.3 1684.01  5038.3  1686.5  5127.2 1688.82  5137.9 1690.37  5164.3 1697.81
  5225.1  1697.2  5280.1 1698.48  5351.7 1704.72  5376.3 1706.81  5390.4 1710.48
  5397.5 1715.36  5404.5 1718.45  5447.3 1733.56  5468.6 1745.67  5489.9 1755.02
  5543.3 1775.63  5554.5 1776.96  5578.8 1782.64  5617.5 1797.39    5652 1801.53
#Mann= 10 ,-1 , 0
  4160.3      .1       0  4186.7     .07       0  4297.9      .1       0
  4610.3    .035       0  4887.6     .07       0  4968.8    .035       0
  5012.8    .035       0  5028.3    .035       0  5225.1    .035       0
  5351.7      .1       0
#Block Obstruct= 2 , 0
         4727.78 1698.96
Bank Sta=5012.8,5028.3
XS Rating Curve= 0 ,0
Exp/Cntr=0.3,0.1

Type RM Length L Ch R = 1 ,8317    ,477,477,477
BEGIN DESCRIPTION:
Bear Creek 17.0
END DESCRIPTION:
XS GIS Cut Line= 3
      1901924.98     13933321.29        1902475.       13932275.
      1902825.03     13931874.97
#Sta/Elev= 30
  3817.7 1729.23  3922.2  1723.7  3968.5  1721.9  3981.7    1718  4012.5 1718.69
  4029.2 1716.48  4063.4 1706.81  4100.7 1693.31  4155.8 1690.72  4173.6 1693.19
  4573.3 1690.72  4610.7 1691.56  4798.9 1695.06  4859.9 1694.81  4917.5 1691.54
  4973.3 1681.84  4973.8 1681.34  4988.8 1681.84  4998.8 1682.62  5074.4 1688.89
  5152.9 1706.26  5168.8 1709.33  5214.3 1724.67  5269.7  1737.8  5299.2 1749.72
  5321.5  1755.5  5393.3 1767.94  5457.1 1783.97  5492.9 1796.51  5531.3 1800.34
#Mann= 11 ,-1 , 0
  3817.7      .1       0  3922.2    .035       0  4029.2      .1       0
  4173.6    .035       0  4573.3     .07       0  4610.7    .035       0
  4798.9    .035       0  4973.3    .035       0  4988.8    .035       0
  4998.8    .035       0  5152.9      .1       0
#Block Obstruct= 2 , 0
         4804.11 1695.34
Bank Sta=4973.3,4988.8
XS Rating Curve= 0 ,0
Exp/Cntr=0.3,0.1

Type RM Length L Ch R = 1 ,7840    ,451,451,451
BEGIN DESCRIPTION:
Bear Creek 16.0
END DESCRIPTION:
XS GIS Cut Line= 3
      1902007.83     13933394.54      1902673.74     13932679.99
        1903075.       13932075.
#Sta/Elev= 30
  4024.7 1726.28  4102.8  1720.5  4157.9 1716.21  4173.5 1711.46  4204.7 1711.41
    4247 1697.49    4266 1690.09  4282.5 1689.98  4327.8 1687.95  4368.8 1689.84
  4463.9 1688.76  4504.1 1690.91  4736.5 1690.55    4794 1689.68  4870.3 1684.19
  4926.2 1682.15  4971.1 1676.42  4971.6 1675.92  4986.6 1676.42  4995.8  1679.3
  5058.4 1690.28  5209.1 1697.39  5342.4 1707.78  5464.8 1726.78  5518.8 1749.17
  5558.4 1758.33  5612.4 1767.26  5648.4 1778.29  5668.3 1781.22  5727.4 1795.62
#Mann= 12 ,-1 , 0
  4024.7      .1       0  4102.8    .035       0    4247      .1       0
  4282.5    .035       0  4463.9     .07       0  4736.5    .035       0
  4870.3    .035       0  4971.1    .035       0  4986.6    .035       0
  4995.8      .1       0  5058.4    .035       0  5209.1      .1       0
#Block Obstruct= 2 , 0
            4576 1690.68
Bank Sta=4971.1,4986.6
XS Rating Curve= 0 ,0
Exp/Cntr=0.3,0.1

Type RM Length L Ch R = 1 ,7389    ,481,481,481
BEGIN DESCRIPTION:
Bear Creek 15.0
END DESCRIPTION:
XS GIS Cut Line= 4
      1902276.23     13933818.94      1902589.44     13933595.09
        1902825.       13933075.      1903164.88     13932309.81
#Sta/Elev= 30
  4040.3 1735.11    4130 1713.27  4174.9 1707.97  4211.2 1703.05  4305.3 1695.88
  4416.3 1692.44    4559 1689.36  4731.8 1688.44  4938.8  1687.6  4974.5 1677.87
  4998.1 1677.23  5002.6 1673.57  5003.1 1673.07  5018.7 1673.57  5020.5 1676.82
  5036.9 1675.52  5045.1 1678.07  5074.7 1682.03  5092.7 1684.32  5243.6 1686.13
  5363.4 1691.75  5434.5 1693.16  5447.2 1691.06  5469.5 1694.28  5617.9 1704.02
  5660.6 1714.17  5732.8 1724.59  5745.9 1728.33  5788.6 1748.78  5833.5  1762.2
#Mann= 12 ,-1 , 0
  4040.3      .1       0  4174.9    .035       0  4416.3     .07       0
    4559    .035       0  4731.8     .07       0  4938.8    .035       0
  5002.6    .035       0  5018.7    .035       0  5045.1     .07       0
  5074.7      .1       0  5363.4    .035       0  5469.5      .1       0
Bank Sta=5002.6,5018.7
XS Rating Curve= 0 ,0
Exp/Cntr=0.3,0.1

Type RM Length L Ch R = 1 ,6908    ,627,627,627
BEGIN DESCRIPTION:
Bear Creek 14.0
END DESCRIPTION:
XS GIS Cut Line= 3
      1902574.99     13934175.02        1903275.       13932975.
        1903325.     13932375.05
#Sta/Elev= 30
  3610.4 1727.93  3675.5 1725.85  3751.9 1716.28    3804 1706.41  3915.2 1698.92
  3915.8 1698.88  3926.7 1696.64    3951 1696.46  3980.8 1693.23    4086 1689.58
  4326.7 1684.86  4585.8 1685.73  4726.2 1684.08  4754.8 1683.87  4891.1 1683.89
  4921.1 1680.74  4932.7 1679.26  4957.1 1672.25  4957.6 1671.75  4973.2 1672.25
  5020.9    1674    5051 1678.34  5127.4 1680.26  5213.4  1686.3  5321.9 1694.66
  5439.4  1710.2  5484.5 1721.58  5523.6 1734.82  5574.8 1748.11  5601.7    1752
#Mann= 12 ,-1 , 0
  3610.4     .07       0  3915.2    .035       0  3915.8     .07       0
  4326.7    .035       0  4585.8     .07       0  4726.2    .035       0
  4754.8     .07       0  4921.1    .035       0  4957.1    .035       0
  4973.2    .035       0  5127.4    .035       0  5213.4      .1       0
Bank Sta=4957.1,4973.2
XS Rating Curve= 0 ,0
Exp/Cntr=0.3,0.1

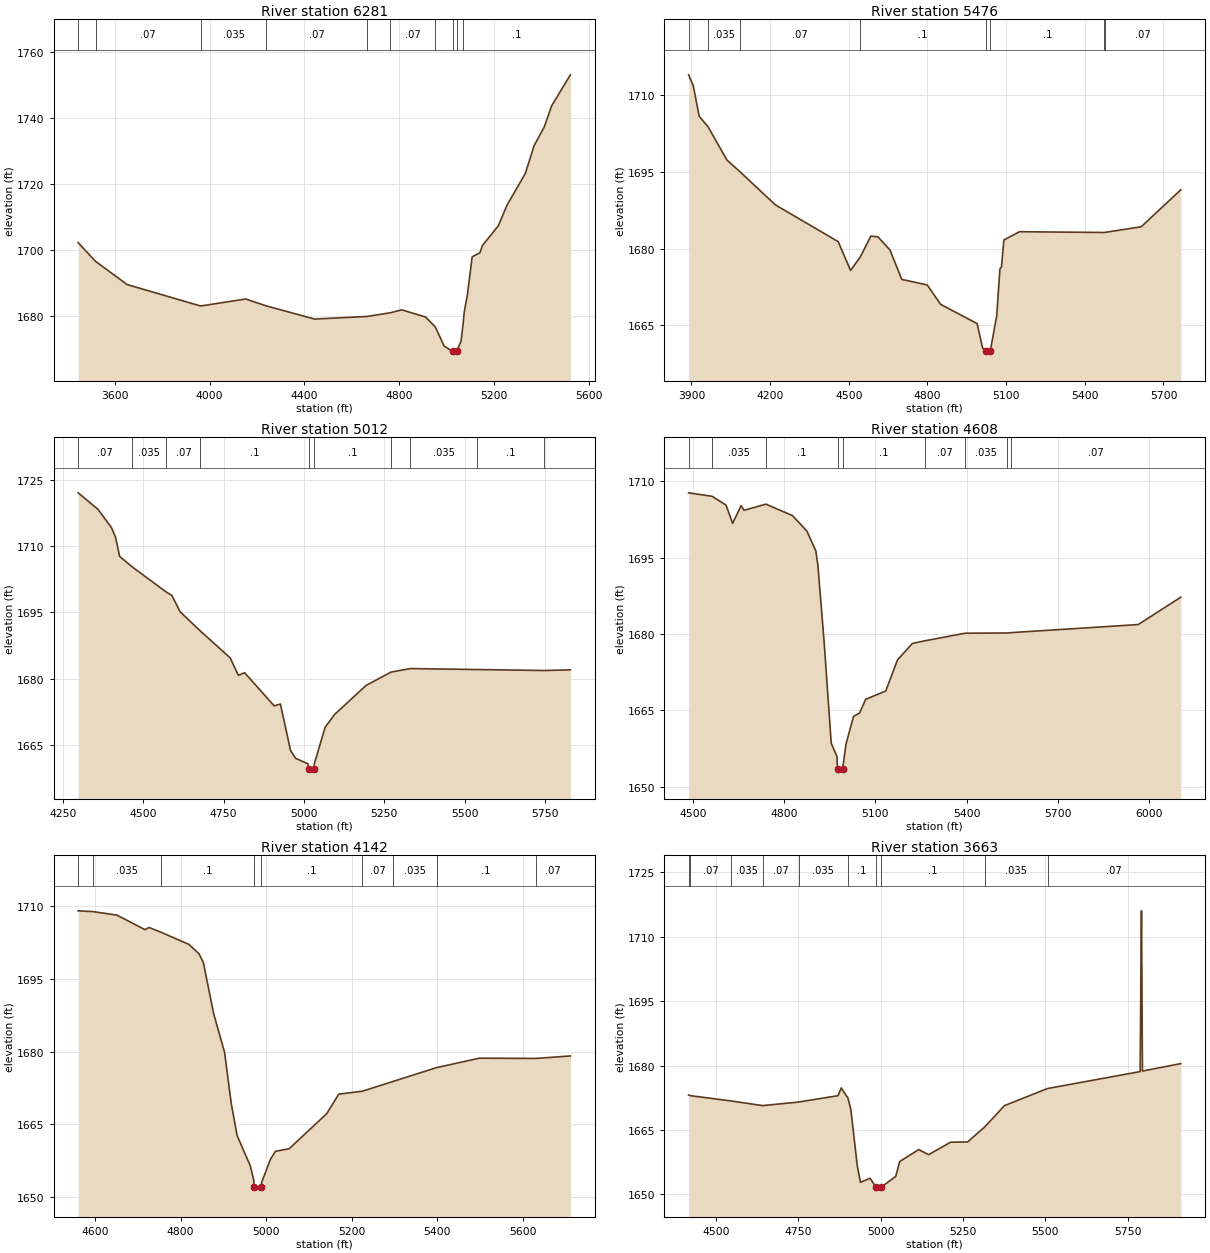
Type RM Length L Ch R = 1 ,6281    ,805,805,805
BEGIN DESCRIPTION:
Bear Creek 13.0
END DESCRIPTION:
XS GIS Cut Line= 4
      1902729.72     13933973.81      1903138.48     13933368.93
      1903851.53     13932938.99      1904310.44     13932712.37
#Sta/Elev= 30
  3446.3 1702.27  3519.5 1696.62  3652.7 1689.57  3962.7 1683.07  4152.3  1685.2
  4239.2 1683.11  4442.4 1679.12  4662.4 1679.89  4762.1 1681.02  4810.2 1681.91
  4910.5 1679.74  4951.7 1676.71  4988.9 1670.93  5024.9 1669.29  5025.4 1668.79
  5041.6 1669.29    5060 1672.43  5068.8 1677.68  5073.4 1681.22  5086.8 1686.43
  5106.9 1697.98  5139.6 1699.21  5150.4 1701.43  5217.3 1707.39  5253.3 1713.56
  5331.1 1723.26  5367.9 1731.65  5411.4 1737.46  5441.5 1743.69  5520.8 1753.14
#Mann= 10 ,-1 , 0
  3446.3    .035       0  3519.5     .07       0  3962.7    .035       0
  4239.2     .07       0  4662.4    .035       0  4762.1     .07       0
  4951.7    .035       0  5024.9    .035       0  5041.6    .035       0
  5068.8      .1       0
#XS Ineff= 2 , 0
         4115.68 1684.51
Permanent Ineff=
       F       F
Bank Sta=5024.9,5041.6
XS Rating Curve= 0 ,0
Exp/Cntr=0.3,0.1

Type RM Length L Ch R = 1 ,5476    ,464,464,464
BEGIN DESCRIPTION:
Bear Creek 12.0
END DESCRIPTION:
XS GIS Cut Line= 5
      1902691.18     13934063.72      1903213.85     13933529.86
        1903575.       13933575.        1903775.       13933575.
      1904289.92     13933339.98
#Sta/Elev= 30
  3888.9 1714.01  3906.7  1711.9  3929.4  1705.9  3963.2 1703.85  4035.3 1697.33
  4083.5 1695.12  4219.9 1688.57  4459.4 1681.38  4506.6 1675.75  4543.8 1678.38
  4583.8 1682.46  4610.9 1682.32  4656.6 1679.77    4702 1673.99  4798.7 1672.92
  4850.1 1669.11  4989.2 1665.35  5010.3 1660.56  5022.9 1660.07  5023.4 1659.57
  5039.6 1660.07  5064.1  1666.9  5076.1 1676.01  5082.3 1676.47  5091.3  1681.7
  5151.1 1683.32  5474.3 1683.17  5475.5 1683.18  5614.7 1684.28    5766 1691.52
#Mann= 8 ,-1 , 0
  3888.9     .07       0  3963.2    .035       0  4083.5     .07       0
  4543.8      .1       0  5022.9     .05       0  5039.6      .1       0
  5474.3    .035       0  5475.5     .07       0
Bank Sta=5022.9,5039.6
XS Rating Curve= 0 ,0
Exp/Cntr=0.3,0.1

Type RM Length L Ch R = 1 ,5012    ,404,404,404
BEGIN DESCRIPTION:
Bear Creek 11.0
END DESCRIPTION:
XS GIS Cut Line= 3
      1902662.97     13934157.24      1903338.96     13933916.74
      1904066.94     13933553.87
#Sta/Elev= 30
  4297.8 1722.11  4359.7 1718.36  4401.4 1714.22  4414.2 1712.04  4426.9  1707.7
  4466.2 1705.31  4572.1 1699.63  4589.3 1698.86  4614.8 1695.17  4677.9  1690.8
  4770.5 1684.73  4796.3 1680.74  4815.4 1681.36  4907.7 1673.83  4926.8 1674.26
  4958.4 1663.74  4974.3 1661.94  5012.5 1660.72  5014.6 1659.55  5015.1 1659.05
  5031.4 1659.55  5032.4 1660.73    5066 1668.99    5096 1671.93  5193.3 1678.47
  5270.7 1681.48  5330.2 1682.29  5538.8 1682.07  5748.2 1681.85  5828.7    1682
#Mann= 10 ,-1 , 0
  4297.8     .07       0  4466.2    .035       0  4572.1     .07       0
  4677.9      .1       0  5014.6     .05       0  5031.4      .1       0
  5270.7     .07       0  5330.2    .035       0  5538.8      .1       0
  5748.2     .07       0
Bank Sta=5014.6,5031.4
XS Rating Curve= 0 ,0
Exp/Cntr=0.3,0.1

Type RM Length L Ch R = 1 ,4608    ,466,466,466
BEGIN DESCRIPTION:
Bear Creek 10.0
END DESCRIPTION:
XS GIS Cut Line= 4
      1903132.84     13934509.83      1903368.93     13934452.05
        1903525.       13934225.       1904333.3     13933478.57
#Sta/Elev= 30
  4485.9  1707.7  4563.9 1707.01  4609.2 1705.28  4630.8 1701.71  4658.6 1705.19
  4668.2 1704.27  4740.2 1705.48  4827.6 1703.23  4874.9  1700.2  4904.4 1696.31
  4911.3 1693.38  4931.4 1678.63    4955 1658.55  4973.8 1655.97  4975.7 1653.57
  4976.2 1653.07  4992.5 1653.57  5003.6 1658.37  5028.4 1663.82  5048.2 1664.47
  5068.2 1667.16  5134.5 1668.81  5172.7 1674.87  5221.7 1678.13  5262.9 1678.65
  5395.2 1680.14  5533.5 1680.19  5547.5 1680.26  5964.5 1681.84  6104.7 1687.21
#Mann= 9 ,-1 , 0
  4485.9     .07       0  4563.9    .035       0  4740.2      .1       0
  4975.7     .05       0  4992.5      .1       0  5262.9     .07       0
  5395.2    .035       0  5533.5      .1       0  5547.5     .07       0
Bank Sta=4975.7,4992.5
XS Rating Curve= 0 ,0
Exp/Cntr=0.3,0.1

Type RM Length L Ch R = 1 ,4142    ,479,479,479
BEGIN DESCRIPTION:
Bear Creek 9.0
END DESCRIPTION:
XS GIS Cut Line= 3
      1903485.44     13934740.44        1903875.       13934525.
       1904075.9     13933848.67
#Sta/Elev= 30
  4560.7 1709.07  4595.2 1708.91  4651.2 1708.19    4717 1705.18  4726.6 1705.63
  4754.3 1704.65  4819.1 1702.17  4843.1 1700.23  4853.4 1698.39  4877.4 1687.88
    4903 1679.87  4918.6 1669.32  4932.3 1662.68  4963.1 1656.44  4971.2 1653.49
  4971.9 1652.12  4972.4 1651.62  4988.7 1652.12  4989.8 1653.04  5010.3 1657.79
  5022.1 1659.44    5054 1659.96  5141.7 1667.19  5169.9 1671.23  5225.1 1671.83
  5296.8 1673.85  5398.5  1676.7  5498.5 1678.65  5630.4  1678.6  5711.4 1679.11
#Mann= 9 ,-1 , 0
  4560.7     .07       0  4595.2    .035       0  4754.3      .1       0
  4971.9     .05       0  4988.7      .1       0  5225.1     .07       0
  5296.8    .035       0  5398.5      .1       0  5630.4     .07       0
Bank Sta=4971.9,4988.7
XS Rating Curve= 0 ,0
Exp/Cntr=0.3,0.1

Type RM Length L Ch R = 1 ,3663    ,446,446,446
BEGIN DESCRIPTION:
Bear Creek 8.0
END DESCRIPTION:
XS GIS Cut Line= 4
      1903843.04     13934902.39      1904181.41     13934948.51
        1904275.       13934725.      1904405.47      13933822.6
#Sta/Elev= 30
  4416.3 1673.15  4421.5 1672.98  4545.4 1671.74  4641.2 1670.66  4750.4 1671.49
  4870.3 1672.97    4880 1674.78  4900.5 1672.41  4909.3 1669.75  4928.8 1656.71
  4938.6  1652.8  4967.8 1653.74  4985.4 1651.71  4985.9 1651.21  5002.2 1651.71
  5045.7 1654.17  5057.9 1657.65  5115.5 1660.42  5145.8 1659.24  5212.5 1662.14
    5264 1662.19  5317.1 1665.77  5376.2 1670.66  5506.9 1674.64  5788.4 1678.58
  5790.7 1701.64  5792.4 1716.02  5794.9  1684.4  5795.5 1678.71  5911.9 1680.44
#Mann= 10 ,-1 , 0
  4416.3      .1       0  4421.5     .07       0  4545.4    .035       0
  4641.2     .07       0  4750.4    .035       0  4900.5      .1       0
  4985.4     .05       0  5002.2      .1       0  5317.1    .035       0
  5506.9     .07       0
Bank Sta=4985.4,5002.2
XS Rating Curve= 0 ,0
Exp/Cntr=0.3,0.1

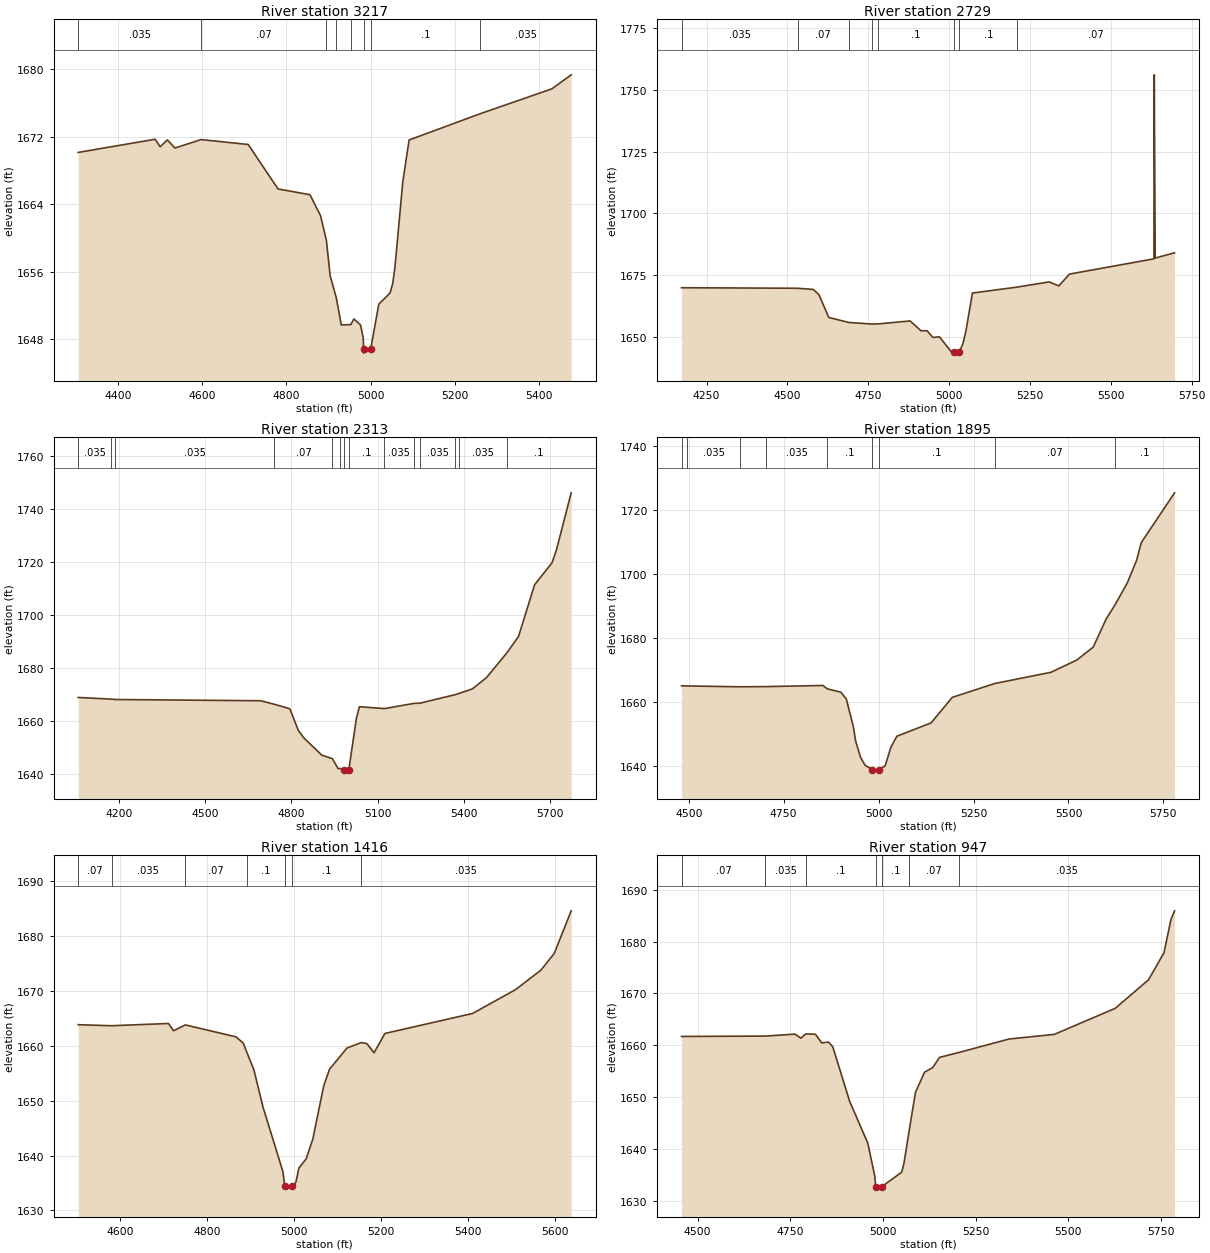
Type RM Length L Ch R = 1 ,3217    ,488,488,488
BEGIN DESCRIPTION:
Bear Creek 7.0
END DESCRIPTION:
XS GIS Cut Line= 5
       1904289.7     13935054.15      1904376.48     13935029.67
      1904539.42     13934731.73        1904625.       13934475.
      1904605.71     13934003.86
#Sta/Elev= 30
    4305 1670.12    4488 1671.68  4499.9 1670.79    4517  1671.6  4535.1 1670.64
  4596.9 1671.64  4709.1 1671.06    4780  1665.8  4855.9 1665.12  4881.2 1662.63
    4895 1659.72    4904 1655.51  4918.4 1652.96  4930.4 1649.71  4953.1 1649.76
  4960.3 1650.42  4976.1 1649.72  4982.6 1648.18  4983.4 1646.88  4983.9 1646.38
  5000.4 1646.88  5019.6 1652.17  5046.3 1653.49  5052.6 1654.58  5057.9 1656.53
  5076.6 1666.62  5091.6 1671.59  5260.7  1674.7  5430.9 1677.64  5476.9  1679.3
#Mann= 8 ,-1 , 0
    4305    .035       0  4596.9     .07       0    4895      .1       0
  4918.4     .07       0  4953.1      .1       0  4983.4     .05       0
  5000.4      .1       0  5260.7    .035       0
Bank Sta=4983.4,5000.4
XS Rating Curve= 0 ,0
Exp/Cntr=0.3,0.1

Type RM Length L Ch R = 1 ,2729    ,416,416,416
BEGIN DESCRIPTION:
Bear Creek 6.0
END DESCRIPTION:
XS GIS Cut Line= 5
      1904541.21       13935163.      1904651.77     13935120.48
      1904892.51     13934939.99        1905075.       13934575.
      1905091.83     13933878.01
#Sta/Elev= 30
  4172.5 1669.87  4531.1 1669.66  4580.1 1669.17  4597.6 1667.02  4627.8 1657.83
  4689.7  1655.8  4761.9 1655.15  4781.5 1655.22  4879.4 1656.42  4912.9 1652.44
  4931.9 1652.43  4949.8 1649.73    4970 1649.97  5006.1 1644.04  5014.5 1643.87
    5015 1643.37  5031.6 1643.87  5042.1 1647.02  5051.1 1651.77  5072.1 1667.72
    5211 1670.14  5309.2 1672.23  5339.2 1670.61  5372.2  1675.4  5633.3 1681.58
  5633.9 1728.69  5634.3 1756.15  5636.3 1705.06  5637.3 1681.89  5697.1 1684.03
#Mann= 8 ,-1 , 0
  4172.5    .035       0  4531.1     .07       0  4689.7      .1       0
  4761.9     .07       0  4781.5      .1       0  5014.5     .05       0
  5031.6      .1       0    5211     .07       0
Bank Sta=5014.5,5031.6
XS Rating Curve= 0 ,0
Exp/Cntr=0.3,0.1

Type RM Length L Ch R = 1 ,2313    ,418,418,418
BEGIN DESCRIPTION:
Bear Creek 5.0
END DESCRIPTION:
XS GIS Cut Line= 6
      1904638.97     13935366.47      1904777.84     13935351.98
      1905116.05     13935289.53        1905325.       13934875.
      1905646.64      13934478.7      1905824.97     13934294.28
#Sta/Elev= 30
  4058.3 1668.95  4172.8 1668.33    4188 1668.18  4693.9 1667.71  4740.7 1666.37
  4794.5 1664.69  4823.5 1656.63  4841.7 1653.87  4905.5 1647.17  4942.6 1645.84
  4962.6 1642.04  4969.6 1642.16  4982.5 1641.64    4983 1641.14  4999.6 1641.64
  5026.1 1661.16  5036.5 1665.46  5123.5 1664.75    5227 1666.73    5247 1666.79
  5370.5 1670.04  5382.2 1670.45  5428.9 1672.16  5478.3 1676.43  5549.1 1685.77
  5589.8 1691.97  5645.7  1711.5  5706.3 1719.79  5722.2 1724.85    5773 1746.22
#Mann= 14 ,-1 , 0
  4058.3    .035       0  4172.8     .07       0    4188    .035       0
  4740.7     .07       0  4942.6      .1       0  4969.6      .1       0
  4982.5     .05       0  4999.6      .1       0  5123.5    .035       0
    5227     .07       0    5247    .035       0  5370.5     .07       0
  5382.2    .035       0  5549.1      .1       0
Bank Sta=4982.5,4999.6
XS Rating Curve= 0 ,0
Exp/Cntr=0.3,0.1

Type RM Length L Ch R = 1 ,1895    ,479,479,479
BEGIN DESCRIPTION:
Bear Creek 4.0
END DESCRIPTION:
XS GIS Cut Line= 6
      1905306.92     13935496.02      1905421.07     13935441.46
      1905583.34     13935291.63        1905625.       13935125.
      1905710.05     13934804.13      1905815.06     13934369.63
#Sta/Elev= 30
  4481.2 1665.01  4496.8 1664.97  4635.1 1664.71    4703 1664.77  4853.2 1665.12
  4865.2 1664.06  4900.4 1663.04    4915 1660.92  4933.6 1652.21  4939.7 1647.65
  4952.4 1642.66  4964.5 1640.13  4983.8 1638.81  4984.3 1638.31  5000.9 1638.81
  5017.1 1639.94  5032.6 1645.83  5048.2 1649.24  5138.2  1653.4    5194  1661.4
  5305.7 1665.73    5454 1669.25  5521.9 1673.09  5565.2 1677.13  5599.1 1685.91
  5621.4 1690.14  5654.7 1697.16  5679.3 1704.28  5691.7 1709.84  5779.3 1725.43
#Mann= 9 ,-1 , 0
  4481.2     .07       0  4496.8    .035       0  4635.1     .07       0
    4703    .035       0  4865.2      .1       0  4983.8     .05       0
  5000.9      .1       0  5305.7     .07       0  5621.4      .1       0
Bank Sta=4983.8,5000.9
XS Rating Curve= 0 ,0
Exp/Cntr=0.3,0.1

Type RM Length L Ch R = 1 ,1416    ,469,469,469
BEGIN DESCRIPTION:
Bear Creek 3.0
END DESCRIPTION:
XS GIS Cut Line= 6
      1905664.42      13935504.7      1905760.85     13935459.77
       1905951.2      13935348.8        1906075.       13935225.
        1906175.       13935025.      1906266.32     13934626.84
#Sta/Elev= 30
  4502.7 1663.85  4579.5 1663.66  4710.3 1664.07  4722.2 1662.74    4749 1663.81
  4865.4 1661.64  4882.3  1660.5  4890.8 1658.78  4906.8 1655.63    4928 1648.77
  4973.7 1637.02  4977.8 1634.37  4978.3 1633.87    4995 1634.37  5003.4 1635.12
  5010.3 1637.71  5027.1  1639.4  5042.4 1643.02  5067.3 1652.65  5080.8 1655.73
    5121  1659.6  5154.1  1660.6  5166.9 1660.39  5183.2 1658.73  5208.2 1662.25
  5409.9  1665.9  5508.2 1670.22  5566.9 1673.79  5597.7 1676.85  5636.6 1684.61
#Mann= 7 ,-1 , 0
  4502.7     .07       0  4579.5    .035       0    4749     .07       0
  4890.8      .1       0  4977.8     .05       0    4995      .1       0
  5154.1    .035       0
Bank Sta=4977.8,4995
XS Rating Curve= 0 ,0
Exp/Cntr=0.3,0.1

Type RM Length L Ch R = 1 ,947     ,468,468,468
BEGIN DESCRIPTION:
Bear Creek 2.0
END DESCRIPTION:
XS GIS Cut Line= 5
       1906011.4      13935689.3      1906348.55     13935551.45
        1906475.       13935425.        1906525.       13935225.
      1906599.13     13934649.28
#Sta/Elev= 30
  4456.9 1661.72  4682.8 1661.79  4762.7 1662.17  4778.8 1661.39    4792 1662.22
    4818 1662.14  4835.1 1660.48  4853.2 1660.64  4864.8 1659.73  4910.3 1649.23
  4959.3 1641.16  4978.2 1634.77  4980.4 1632.81  4980.9 1632.31  4997.6 1632.81
  5050.7 1635.58  5056.9 1637.33  5070.9  1643.6  5087.8 1650.95  5112.5 1654.85
  5134.4 1655.73  5152.7 1657.69    5206 1658.65  5339.9 1661.22  5462.4 1662.12
  5626.7 1667.14  5716.5 1672.64    5758 1677.83    5777 1684.26  5786.6 1685.92
#Mann= 7 ,-1 , 0
  4456.9     .07       0  4682.8    .035       0    4792      .1       0
  4980.4     .05       0  4997.6      .1       0  5070.9     .07       0
    5206    .035       0
Bank Sta=4980.4,4997.6
XS Rating Curve= 0 ,0
Exp/Cntr=0.3,0.1

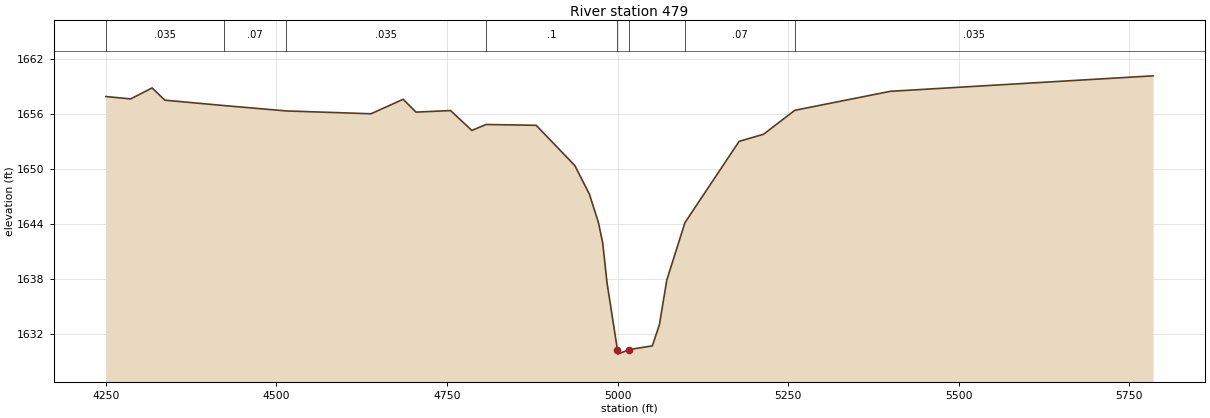
Type RM Length L Ch R = 1 ,479     ,0,0,0
BEGIN DESCRIPTION:
Bear Creek 1.0
END DESCRIPTION:
XS GIS Cut Line= 4
      1906164.06     13935848.71        1906875.       13935625.
        1907025.       13935475.      1907125.85     13934906.72
#Sta/Elev= 30
  4250.1 1657.89  4286.4 1657.63  4317.8 1658.83  4336.6 1657.49  4422.5 1656.91
  4514.2 1656.32  4638.6 1656.01  4685.7 1657.59  4704.6 1656.19  4755.2 1656.36
  4786.4 1654.19  4807.2 1654.84  4880.7 1654.75  4937.3 1650.36  4958.6 1647.25
  4971.9 1644.15  4978.2 1641.89  4984.5 1637.56  4999.7 1630.28  5000.2 1629.78
  5017.1 1630.28  5050.9 1630.68  5061.3    1633  5072.1 1637.87  5098.7 1644.13
  5178.1    1653  5213.8 1653.77  5259.8 1656.39  5399.7 1658.46  5784.7 1660.15
#Mann= 8 ,-1 , 0
  4250.1    .035       0  4422.5     .07       0  4514.2    .035       0
  4807.2      .1       0  4999.7     .05       0  5017.1      .1       0
  5098.7     .07       0  5259.8    .035       0
Bank Sta=4999.7,5017.1
XS Rating Curve= 0 ,0
Exp/Cntr=0.3,0.1

Chan Stop Cuts=-1
Use User Specified Reach Order=0
Composite Channel Slope=5