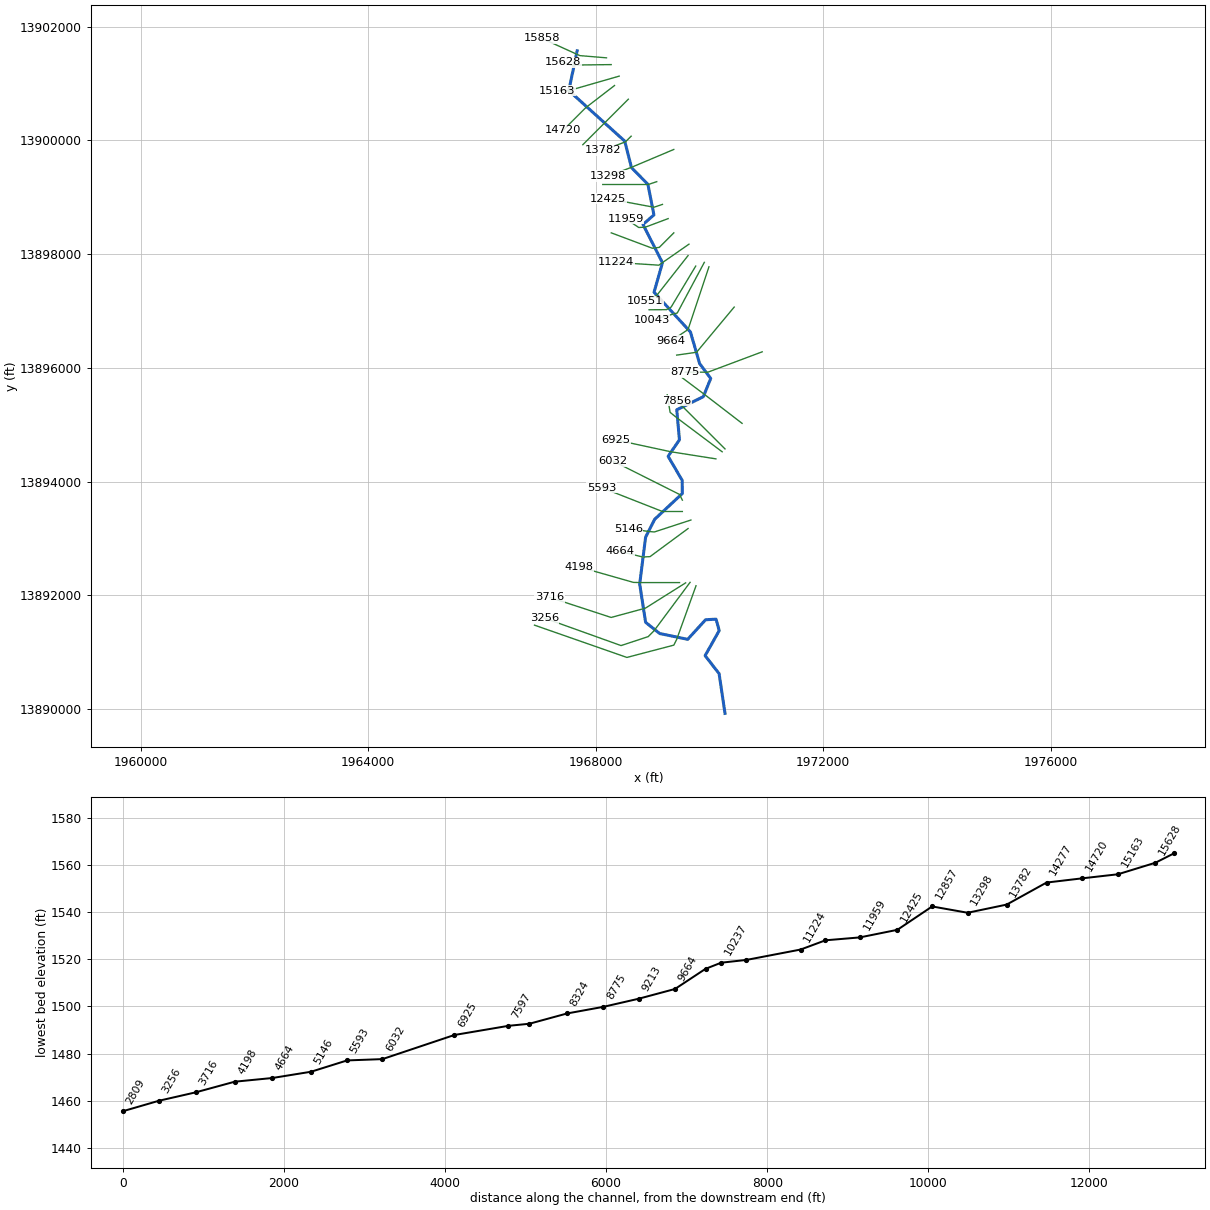
--- Bluff Creek.prj (project) ---

Proj Title=Bluff Creek Base Level Engineering
Current Plan=p01
Default Exp/Contr=0.3,0.1
English Units
Geom File=g01
Flow File=f01
Plan File=p01
BEGIN DESCRIPTION:
Bluff Creek
END DESCRIPTION:

--- Bluff Creek.p01 (plan) ---

Plan Title=Multiple Run
Short Identifier=Multiple
Geom File=g01
Flow File=f01
Subcritical Flow
K Sum by GR= 0
Std Step Tol= 0.01
Critical Tol= 0.01
Num of Std Step Trials= 20
Max Error Tol= 0.3
Flow Tol Ratio= 0.001
Split Flow NTrial= 30
Split Flow Tol= 0.02
Split Flow Ratio= 0.02
Log Output Level= 0
Friction Slope Method= 1
Unsteady Friction Slope Method= 2
Unsteady Bridges Friction Slope Method= 1
Parabolic Critical Depth
Global Vel Dist=  1 , 1 , 1
Global Log Level= 0
CheckData=True
Encroach Param= -1, 0, 0, 0
BEGIN DESCRIPTION:
Multiple Run
END DESCRIPTION:

--- Bluff Creek.f01 (steady flow) ---

Flow Title=Multiple
Number of Profiles=7
Profile Names=10-year,25-year,50-year,1pct_min,100-year,1pct_plu,500-year
River Rch & RM= Bluff Creek,Reach-1,15858
    1963    3473    4965    3433    6850   13667   12919
River Rch & RM= Bluff Creek,Reach-1,8324
    2470    4409    6343    4408    8796   17550   16768
River Rch & RM= Bluff Creek,Reach-1,5146
    2914    5241    7576    5288   10551   21053   20292
River Rch & RM= Bluff Creek,Reach-1,3716
    4314    7854   11440    8021   16005   31934   30977
River Rch & RM= Bluff Creek,Reach-1,1392
    3461    6261    9086    6362   12694   25327   24570
Boundary for River Rch & Prof#=Bluff Creek,Reach-1,1
Up Type=0
Dn Type=3
Dn Slope=0.005
Boundary for River Rch & Prof#=Bluff Creek,Reach-1,2
Up Type=0
Dn Type=3
Dn Slope=0.005
Boundary for River Rch & Prof#=Bluff Creek,Reach-1,3
Up Type=0
Dn Type=3
Dn Slope=0.005
Boundary for River Rch & Prof#=Bluff Creek,Reach-1,4
Up Type=0
Dn Type=3
Dn Slope=0.005
Boundary for River Rch & Prof#=Bluff Creek,Reach-1,5
Up Type=0
Dn Type=3
Dn Slope=0.005
Boundary for River Rch & Prof#=Bluff Creek,Reach-1,6
Up Type=0
Dn Type=3
Dn Slope=0.005
Boundary for River Rch & Prof#=Bluff Creek,Reach-1,7
Up Type=0
Dn Type=3
Dn Slope=0.005

--- Bluff Creek.g01 (geometry) ---

Geom Title=Existing Conditions

River Reach=Bluff Creek,Reach-1
Reach XY= 30
      1967675.00     13901575.00      1967528.13     13900876.63
      1968511.37     13899988.21      1968630.45     13899522.53
      1968919.46     13899227.42      1969024.67     13898690.03
      1968832.87     13898521.79      1969175.21     13897850.08
      1969027.06     13897330.85      1969667.14     13896631.19
      1969828.55     13896076.29      1970023.81     13895814.50
      1969895.13     13895494.77      1969426.62     13895263.17
      1969473.81     13894735.50      1969274.63     13894445.20
      1969521.40     13894023.51      1969524.34     13893790.83
      1969038.40     13893338.31      1968878.74     13893023.45
      1968774.80     13892199.92      1968878.54     13891526.46
      1969126.58     13891328.82      1969619.15     13891227.06
      1969933.48     13891571.49      1970117.26     13891581.55
      1970173.38     13891381.03      1969925.24     13890940.22
      1970171.18     13890623.42      1970275.00     13889925.00

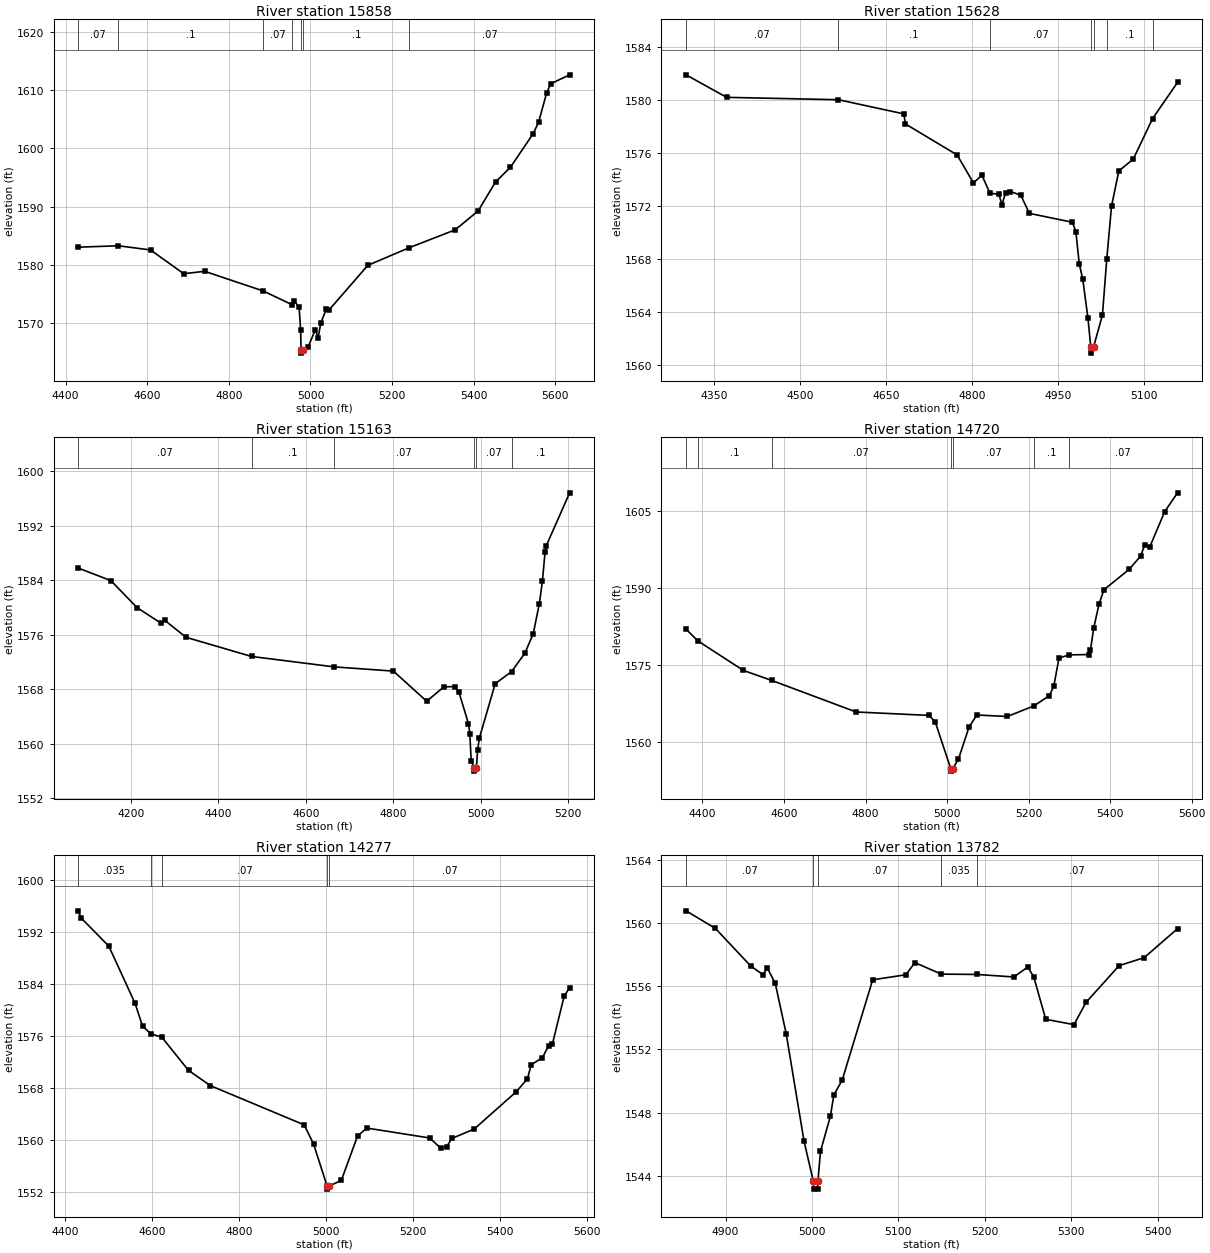
Type RM Length L Ch R = 1,15858,230,230,230
BEGIN DESCRIPTION:
Bluff Creek 33.0
END DESCRIPTION:
XS GIS Cut Line= 3
      1968191.18     13901452.48      1967722.38     13901491.55
      1967054.01     13901795.35
#Sta/Elev= 30
  4430.5 1583.04  4529.2 1583.28  4608.0 1582.56  4689.3 1578.48  4740.5 1578.89
  4884.3 1575.51  4954.0 1573.18  4960.6 1573.77  4972.1 1572.72  4975.8 1568.88
  4976.9 1565.33  4977.3 1564.83  4981.9 1565.33  4993.9 1565.83  5012.0 1568.89
  5018.6 1567.41  5025.2 1570.00  5038.4 1572.36  5045.0 1572.21  5140.5 1579.92
  5242.4 1582.96  5354.7 1586.02  5410.8 1589.27  5453.6 1594.26  5489.8 1596.75
  5545.9 1602.57  5559.0 1604.51  5578.8 1609.57  5588.6 1611.12  5635.1 1612.66
#Mann=7,-1,0
  4430.5    0.07       0  4529.2     0.1       0  4884.3    0.07       0
  4954.0     0.1       0  4976.9    0.05       0  4981.9     0.1       0
  5242.4    0.07       0
Bank Sta=4976.9,4981.9
Exp/Cntr=0.3,0.1

Type RM Length L Ch R = 1,15628,465,465,465
BEGIN DESCRIPTION:
Bluff Creek 32.0
END DESCRIPTION:
XS GIS Cut Line= 3
      1968274.01     13901333.61      1967575.00     13901325.00
      1967424.97     13901375.01
#Sta/Elev= 30
  4300.9 1581.88  4371.7 1580.18  4566.7 1580.00  4680.7 1578.93  4683.6 1578.17
  4773.7 1575.83  4802.1 1573.72  4816.9 1574.30  4830.8 1572.95  4846.6 1572.86
  4851.7 1572.08  4858.4 1572.99  4866.7 1573.07  4884.7 1572.79  4899.7 1571.42
  4974.7 1570.75  4980.7 1570.05  4986.7 1567.60  4992.7 1566.47  5001.8 1563.52
  5006.7 1561.37  5007.1 1560.87  5011.8 1561.37  5027.1 1563.75  5034.6 1567.96
  5042.9 1571.95  5055.6 1574.62  5080.9 1575.52  5114.6 1578.58  5158.1 1581.31
#Mann=7,-1,0
  4300.9    0.07       0  4566.7     0.1       0  4830.8    0.07       0
  5006.7    0.05       0  5011.8    0.07       0  5034.6     0.1       0
  5114.6    0.07       0
Bank Sta=5006.7,5011.8
Exp/Cntr=0.3,0.1

Type RM Length L Ch R = 1,15163,443,443,443
BEGIN DESCRIPTION:
Bluff Creek 31.0
END DESCRIPTION:
XS GIS Cut Line= 3
      1968413.67     13901130.55      1967525.00     13900875.00
      1967324.99     13900875.00
#Sta/Elev= 30
  4078.9 1585.80  4154.0 1583.95  4213.6 1580.00  4268.0 1577.73  4277.7 1578.10
  4325.9 1575.63  4475.8 1572.82  4665.1 1571.29  4800.4 1570.67  4876.5 1566.25
  4915.9 1568.36  4940.9 1568.40  4950.3 1567.57  4972.1 1562.96  4975.2 1561.48
  4978.3 1557.54  4985.2 1556.49  4985.6 1555.99  4990.3 1556.49  4992.9 1559.06
  4997.1 1560.85  5033.3 1568.83  5070.6 1570.59  5101.3 1573.31  5120.3 1576.16
  5134.3 1580.57  5141.3 1583.89  5147.3 1588.12  5150.3 1589.10  5203.6 1596.84
#Mann=6,-1,0
  4078.9    0.07       0  4475.8     0.1       0  4665.1    0.07       0
  4985.2    0.05       0  4990.3    0.07       0  5070.6     0.1       0
Bank Sta=4985.2,4990.3
Exp/Cntr=0.3,0.1

Type RM Length L Ch R = 1,14720,443,443,443
BEGIN DESCRIPTION:
Bluff Creek 30.0
END DESCRIPTION:
XS GIS Cut Line= 3
      1968332.16     13900965.48      1967825.00     13900575.00
      1967424.97     13900174.97
#Sta/Elev= 30
  4359.7 1581.99  4388.5 1579.71  4500.4 1573.93  4570.3 1571.97  4776.8 1565.82
  4956.1 1565.15  4971.1 1563.85  5009.0 1554.77  5009.4 1554.27  5014.2 1554.77
  5028.0 1556.62  5054.0 1562.88  5073.1 1565.23  5147.9 1564.94  5213.2 1567.01
  5251.3 1569.03  5261.9 1570.88  5274.6 1576.32  5298.8 1576.97  5347.3 1577.03
  5351.6 1577.84  5360.0 1582.28  5372.8 1586.87  5384.9 1589.69  5446.5 1593.65
  5474.6 1596.23  5484.7 1598.37  5497.4 1598.06  5534.0 1604.96  5565.5 1608.61
#Mann=7,-1,0
  4359.7    0.07       0  4388.5     0.1       0  4570.3    0.07       0
  5009.0    0.05       0  5014.2    0.07       0  5213.2     0.1       0
  5298.8    0.07       0
Bank Sta=5009,5014.2
Exp/Cntr=0.3,0.1

Type RM Length L Ch R = 1,14277,495,495,495
BEGIN DESCRIPTION:
Bluff Creek 29.0
END DESCRIPTION:
XS GIS Cut Line= 3
      1968575.03     13900725.03      1968175.00     13900325.00
      1967775.01     13899925.01
#Sta/Elev= 30
  4429.5 1595.31  4436.6 1594.20  4500.2 1589.87  4560.7 1581.06  4577.7 1577.56
  4596.6 1576.42  4622.6 1575.83  4683.7 1570.75  4734.1 1568.40  4949.9 1562.37
  4971.7 1559.38  5002.4 1552.98  5002.8 1552.48  5007.7 1552.98  5035.3 1553.81
  5073.0 1560.71  5094.7 1561.87  5239.0 1560.35  5264.4 1558.76  5277.7 1559.02
  5289.9 1560.28  5341.4 1561.74  5438.4 1567.49  5463.8 1569.47  5472.3 1571.62
  5498.3 1572.70  5512.6 1574.58  5521.1 1574.78  5548.2 1582.15  5560.9 1583.51
#Mann=5,-1,0
  4429.5   0.035       0  4596.6     0.1       0  4622.6    0.07       0
  5002.4    0.05       0  5007.7    0.07       0
Bank Sta=5002.4,5007.7
Exp/Cntr=0.3,0.1

Type RM Length L Ch R = 1,13782,484,484,484
BEGIN DESCRIPTION:
Bluff Creek 28.0
END DESCRIPTION:
XS GIS Cut Line= 3
      1968624.98     13900074.98      1968525.00     13899975.00
      1968124.99     13899825.00
#Sta/Elev= 30
  4854.3 1560.78  4888.2 1559.67  4929.2 1557.28  4943.3 1556.74  4948.3 1557.16
  4957.5 1556.19  4970.2 1552.98  4990.7 1546.22  5001.5 1543.65  5001.9 1543.15
  5006.4 1543.15  5006.9 1543.65  5009.8 1545.54  5021.3 1547.77  5025.3 1549.12
  5034.9 1550.05  5070.2 1556.41  5108.6 1556.73  5119.0 1557.50  5149.6 1556.77
  5190.7 1556.75  5233.6 1556.59  5249.6 1557.22  5256.5 1556.60  5270.4 1553.91
  5303.1 1553.57  5317.0 1554.98  5355.3 1557.31  5384.2 1557.81  5422.9 1559.65
#Mann=5,-1,0
  4854.3    0.07       0  5001.5    0.05       0  5006.9    0.07       0
  5149.6   0.035       0  5190.7    0.07       0
Bank Sta=5001.5,5006.9
Exp/Cntr=0.3,0.1

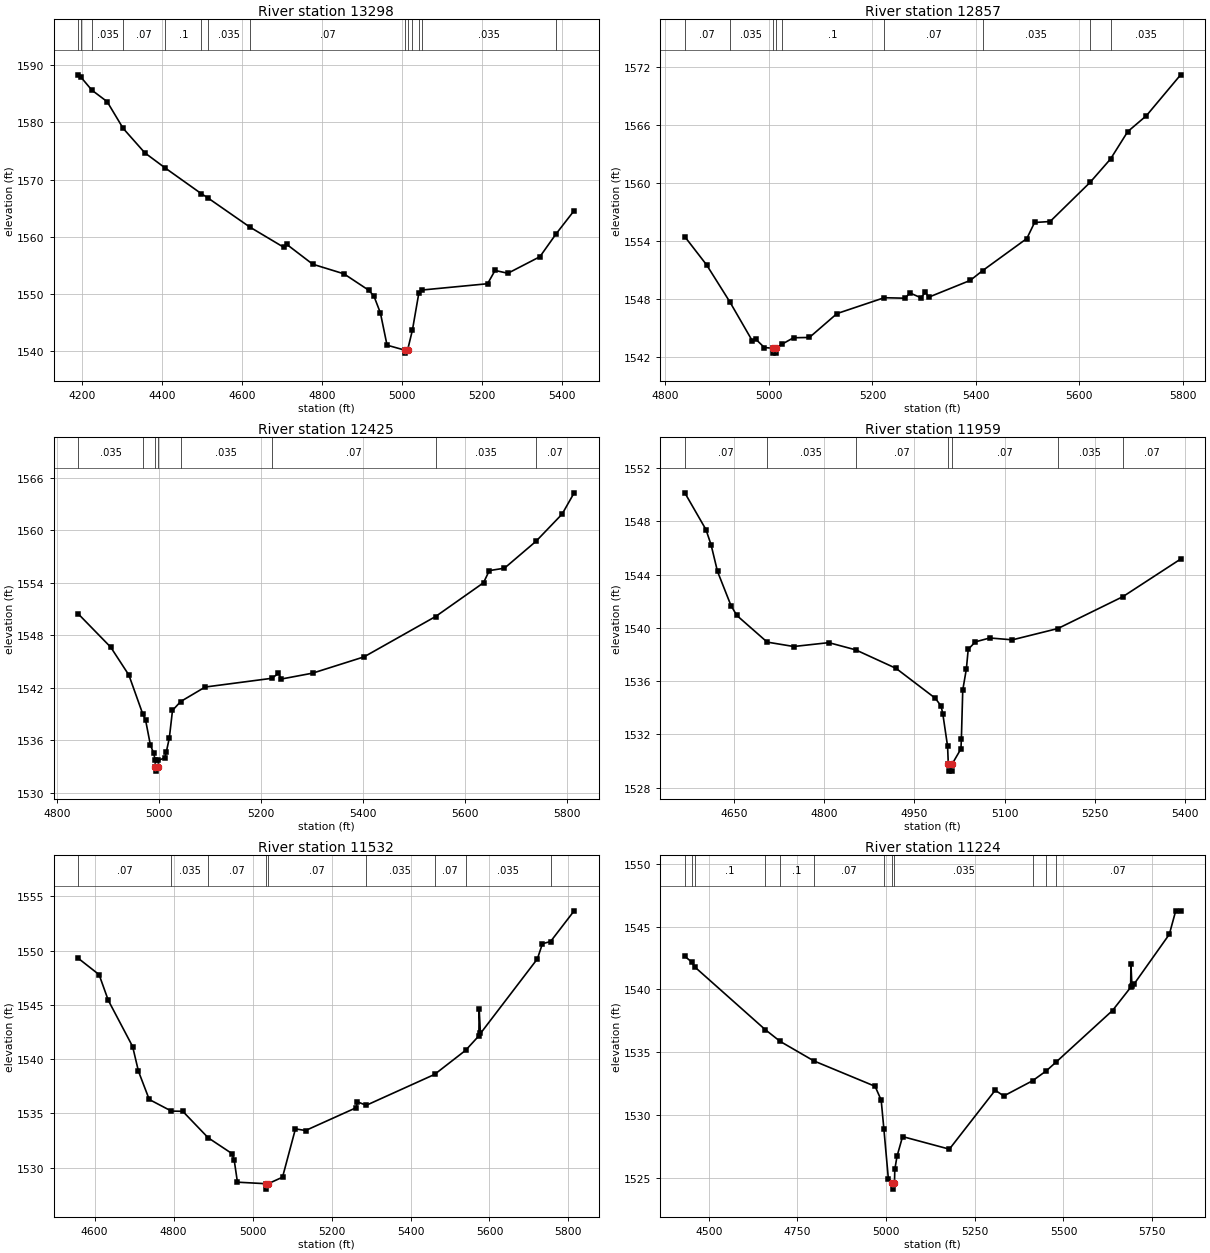
Type RM Length L Ch R = 1,13298,441,441,441
BEGIN DESCRIPTION:
Bluff Creek 27.0
END DESCRIPTION:
XS GIS Cut Line= 3
      1969374.31     13899841.02      1968625.00     13899525.00
      1968225.02     13899375.01
#Sta/Elev= 30
  4190.6 1588.30  4197.2 1587.88  4224.5 1585.62  4262.6 1583.62  4302.7 1578.95
  4357.0 1574.67  4408.3 1572.01  4498.1 1567.55  4513.9 1566.84  4619.4 1561.72
  4705.4 1558.14  4711.9 1558.69  4777.0 1555.22  4855.1 1553.54  4917.0 1550.68
  4930.0 1549.67  4946.3 1546.70  4962.9 1541.08  5008.4 1540.19  5008.9 1539.69
  5014.2 1540.19  5026.4 1543.72  5042.4 1550.17  5050.1 1550.71  5214.4 1551.81
  5233.1 1554.13  5265.2 1553.64  5345.3 1556.53  5385.7 1560.51  5431.0 1564.58
#Mann=14,-1,0
  4190.6   0.035       0  4197.2     0.1       0  4224.5   0.035       0
  4302.7    0.07       0  4408.3     0.1       0  4498.1    0.07       0
  4513.9   0.035       0  4619.4    0.07       0  5008.4    0.05       0
  5014.2    0.07       0  5026.4   0.035       0  5042.4    0.07       0
  5050.1   0.035       0  5385.7    0.07       0
Bank Sta=5008.4,5014.2
Exp/Cntr=0.3,0.1

Type RM Length L Ch R = 1,12857,432,432,432
BEGIN DESCRIPTION:
Bluff Creek 26.0
END DESCRIPTION:
XS GIS Cut Line= 3
      1969075.03     13899275.01      1968925.00     13899225.00
      1968125.05     13899225.00
#Sta/Elev= 30
  4837.5 1554.40  4879.7 1551.48  4924.3 1547.68  4968.2 1543.61  4974.7 1543.80
  4991.2 1542.94  5008.1 1542.86  5008.6 1542.36  5013.5 1542.36  5013.9 1542.86
  5025.8 1543.30  5047.6 1543.95  5078.3 1543.98  5131.6 1546.45  5222.9 1548.09
  5263.0 1548.04  5272.6 1548.58  5293.6 1548.09  5302.6 1548.65  5308.6 1548.14
  5389.0 1549.88  5413.2 1550.90  5498.4 1554.21  5513.4 1555.87  5543.4 1555.97
  5620.5 1560.01  5660.2 1562.44  5693.4 1565.27  5729.4 1566.91  5795.6 1571.14
#Mann=9,-1,0
  4837.5    0.07       0  4924.3   0.035       0  5008.1   0.035       0
  5013.9   0.035       0  5025.8     0.1       0  5222.9    0.07       0
  5413.2   0.035       0  5620.5    0.07       0  5660.2   0.035       0
Bank Sta=5008.1,5013.9
Exp/Cntr=0.3,0.1

Type RM Length L Ch R = 1,12425,466,466,466
BEGIN DESCRIPTION:
Bluff Creek 25.0
END DESCRIPTION:
XS GIS Cut Line= 3
      1969174.99     13898875.00      1969025.00     13898825.00
      1968225.05     13898974.99
#Sta/Elev= 30
  4842.0 1550.44  4905.5 1546.64  4941.1 1543.45  4968.2 1539.01  4973.7 1538.34
  4983.2 1535.47  4989.6 1534.52  4992.7 1533.72  4992.9 1532.96  4993.4 1532.46
  4998.8 1532.96  4999.0 1533.70  5011.3 1533.97  5014.3 1534.61  5020.4 1536.26
  5026.6 1539.41  5042.6 1540.42  5090.6 1542.08  5221.3 1543.08  5234.1 1543.63
  5240.2 1543.00  5301.3 1543.67  5402.0 1545.53  5542.4 1550.15  5636.3 1554.01
  5647.6 1555.40  5677.4 1555.68  5739.1 1558.75  5790.4 1561.87  5814.0 1564.30
#Mann=8,-1,0
  4842.0   0.035       0  4968.2    0.07       0  4992.9    0.05       0
  4998.8    0.07       0  5042.6   0.035       0  5221.3    0.07       0
  5542.4   0.035       0  5739.1    0.07       0
Bank Sta=4992.9,4998.8
Exp/Cntr=0.3,0.1

Type RM Length L Ch R = 1,11959,427,427,427
BEGIN DESCRIPTION:
Bluff Creek 24.0
END DESCRIPTION:
XS GIS Cut Line= 4
      1969274.96     13898624.98      1968875.00     13898475.00
      1968758.52     13898469.10      1968525.05     13898624.97
#Sta/Elev= 30
  4568.1 1550.13  4603.3 1547.37  4611.8 1546.23  4622.5 1544.23  4644.9 1541.67
  4654.6 1540.93  4705.1 1538.93  4749.3 1538.60  4807.6 1538.89  4852.2 1538.35
  4919.4 1536.96  4984.6 1534.72  4994.2 1534.14  4997.2 1533.53  5005.1 1531.11
  5006.3 1529.75  5006.8 1529.25  5011.7 1529.25  5012.2 1529.75  5027.3 1530.92
  5028.0 1531.64  5030.3 1535.33  5036.3 1536.91  5039.4 1538.39  5051.3 1538.95
  5075.3 1539.24  5112.8 1539.10  5188.6 1539.95  5296.6 1542.34  5392.6 1545.16
#Mann=7,-1,0
  4568.1    0.07       0  4705.1   0.035       0  4852.2    0.07       0
  5006.3    0.05       0  5012.2    0.07       0  5188.6   0.035       0
  5296.6    0.07       0
Bank Sta=5006.3,5012.2
Exp/Cntr=0.3,0.1

Type RM Length L Ch R = 1,11532,308,308,308
BEGIN DESCRIPTION:
Bluff Creek 23.0
END DESCRIPTION:
XS GIS Cut Line= 4
      1969375.02     13898375.02      1969118.95     13898118.95
      1968995.72     13898104.73      1968275.01     13898375.00
#Sta/Elev= 30
  4558.6 1549.28  4611.2 1547.78  4634.5 1545.41  4696.1 1541.16  4710.9 1538.88
  4738.2 1536.28  4794.3 1535.21  4823.1 1535.19  4887.5 1532.75  4947.9 1531.29
  4953.5 1530.67  4961.6 1528.66  5033.4 1528.52  5033.9 1528.02  5039.4 1528.52
  5075.8 1529.12  5108.5 1533.57  5134.2 1533.42  5262.3 1535.52  5265.5 1536.07
  5287.7 1535.74  5461.0 1538.59  5539.6 1540.81  5573.1 1542.14  5573.9 1544.63
  5577.1 1542.36  5721.3 1549.23  5734.1 1550.63  5754.7 1550.83  5814.5 1553.66
#Mann=9,-1,0
  4558.6    0.07       0  4794.3   0.035       0  4887.5    0.07       0
  5033.4    0.05       0  5039.4    0.07       0  5287.7   0.035       0
  5461.0    0.07       0  5539.6   0.035       0  5754.7    0.07       0
Bank Sta=5033.4,5039.4
Exp/Cntr=0.3,0.1

Type RM Length L Ch R = 1,11224,673,673,673
BEGIN DESCRIPTION:
Mapping XS e0a44c74
END DESCRIPTION:
XS GIS Cut Line= 3
      1969640.78     13898175.57      1969111.27     13897806.65
      1968360.44     13897854.39
#Sta/Elev= 30
  4432.5 1542.63  4451.9 1542.18  4460.8 1541.78  4659.2 1536.80  4701.5 1535.86
  4796.3 1534.31  4968.9 1532.29  4986.1 1531.19  4993.7 1528.89  5006.3 1524.95
  5017.6 1524.61  5018.1 1524.11  5023.6 1524.61  5024.5 1525.68  5030.7 1526.72
  5046.4 1528.29  5178.3 1527.29  5307.6 1531.98  5331.6 1531.52  5412.7 1532.73
  5451.2 1533.51  5478.5 1534.20  5638.2 1538.32  5689.3 1540.16  5690.1 1542.03
  5693.0 1540.29  5699.1 1540.43  5798.3 1544.38  5816.3 1546.24  5830.2 1546.25
#Mann=12,-1,0
  4432.5     0.1       0  4451.9    0.07       0  4460.8     0.1       0
  4659.2    0.07       0  4701.5     0.1       0  4796.3    0.07       0
  4993.7   0.035       0  5017.6   0.035       0  5023.6   0.035       0
  5412.7    0.07       0  5451.2   0.035       0  5478.5    0.07       0
Bank Sta=5017.6,5023.6
Exp/Cntr=0.3,0.1

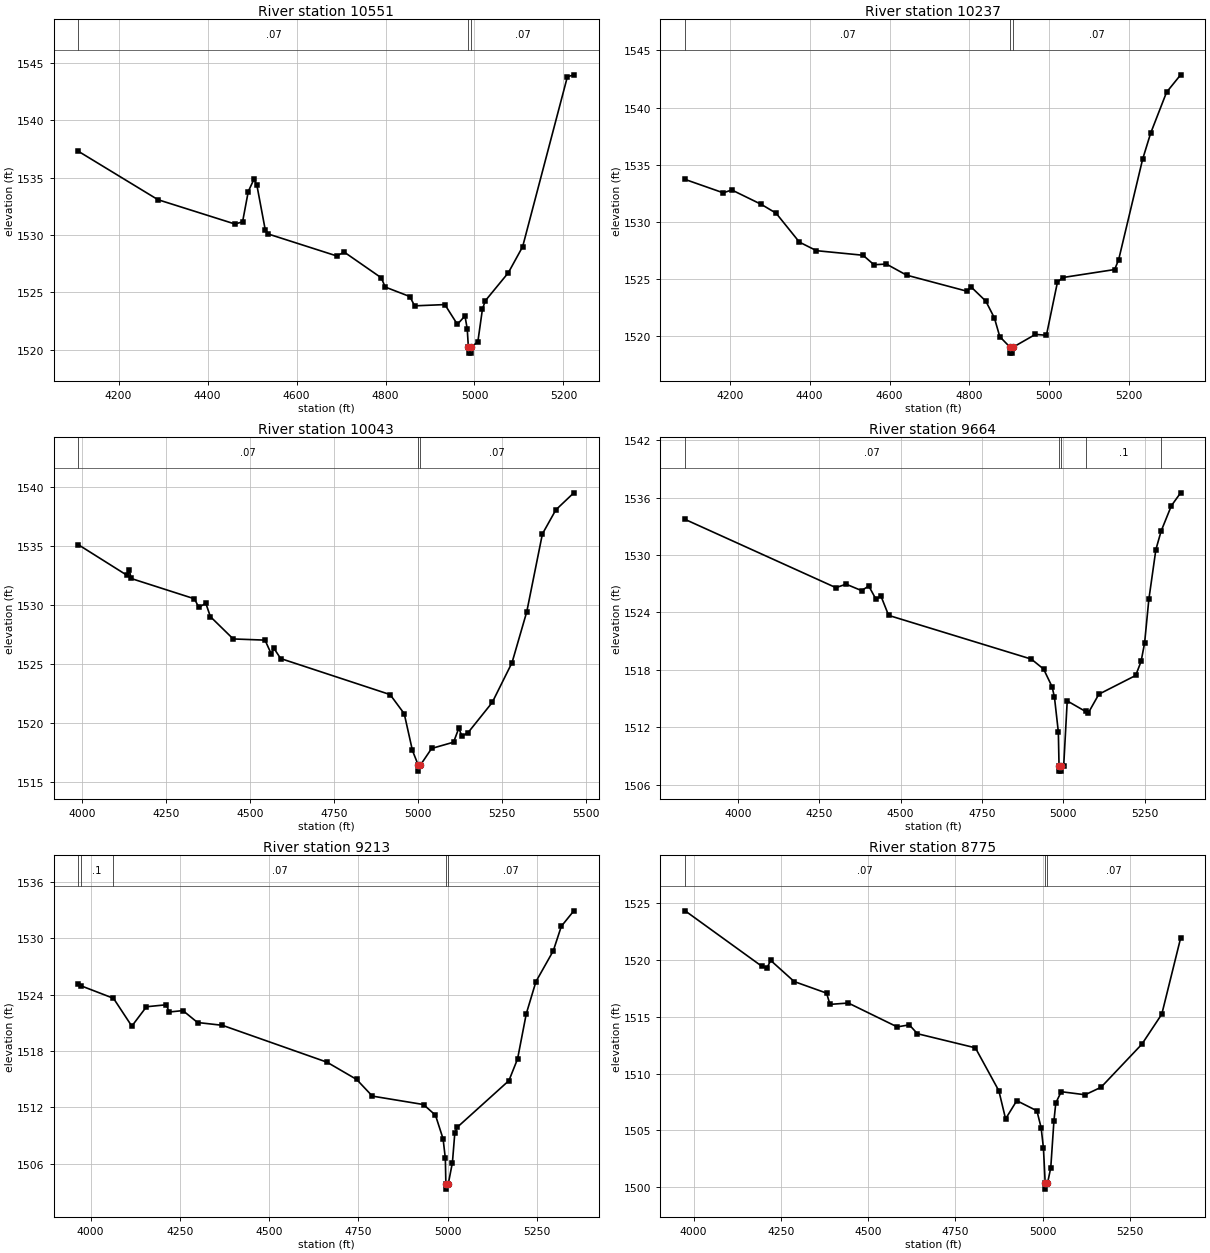
Type RM Length L Ch R = 1,10551,314,314,314
BEGIN DESCRIPTION:
Bluff Creek 22.0
END DESCRIPTION:
XS GIS Cut Line= 3
      1969625.01     13897975.01      1969075.00     13897275.00
      1968875.04     13897175.02
#Sta/Elev= 30
  4109.5 1537.30  4288.5 1533.08  4461.6 1530.96  4478.7 1531.15  4491.5 1533.79
  4504.3 1534.86  4510.9 1534.34  4529.7 1530.45  4536.4 1530.09  4690.2 1528.18
  4707.3 1528.51  4790.6 1526.27  4799.2 1525.47  4854.7 1524.64  4865.4 1523.83
  4933.4 1523.94  4961.5 1522.22  4978.6 1522.95  4983.7 1521.82  4986.3 1520.21
  4986.8 1519.71  4991.9 1519.71  4992.4 1520.21  5007.6 1520.71  5017.9 1523.55
  5024.3 1524.27  5076.0 1526.71  5108.2 1528.98  5208.8 1543.79  5223.3 1543.96
#Mann=3,-1,0
  4109.5    0.07       0  4986.3    0.05       0  4992.4    0.07       0
Bank Sta=4986.3,4992.4
Exp/Cntr=0.3,0.1

Type RM Length L Ch R = 1,10237,194,194,194
BEGIN DESCRIPTION:
Bluff Creek D1
END DESCRIPTION:
XS GIS Cut Line= 4
      1969759.89     13897790.39      1969328.04     13897069.91
      1969245.57     13897024.34      1968939.79     13897022.17
#Sta/Elev= 30
  4088.5 1533.72  4183.9 1532.55  4205.3 1532.80  4279.1 1531.54  4316.1 1530.77
  4374.4 1528.24  4417.2 1527.49  4533.8 1527.09  4561.1 1526.26  4592.1 1526.32
  4642.7 1525.35  4794.3 1523.94  4804.1 1524.32  4840.9 1523.08  4862.4 1521.61
  4875.9 1519.97  4902.1 1519.03  4902.6 1518.53  4907.7 1518.53  4908.2 1519.03
  4965.1 1520.17  4992.6 1520.09  5020.2 1524.73  5033.3 1525.14  5163.3 1525.84
  5173.3 1526.69  5233.3 1535.48  5253.3 1537.75  5293.3 1541.35  5328.5 1542.87
#Mann=3,-1,0
  4088.5    0.07       0  4902.1    0.05       0  4908.2    0.07       0
Bank Sta=4902.1,4908.2
Exp/Cntr=0.3,0.1

Type RM Length L Ch R = 1,10043,379,379,379
BEGIN DESCRIPTION:
Bluff Creek 21.0
END DESCRIPTION:
XS GIS Cut Line= 3
      1969911.62     13897856.54      1969435.87     13896965.64
      1968986.40     13896843.29
#Sta/Elev= 30
  3989.4 1535.10  4133.2 1532.53  4141.2 1532.98  4146.5 1532.24  4335.1 1530.52
  4348.2 1529.80  4369.1 1530.14  4382.7 1529.01  4450.7 1527.12  4545.5 1527.02
  4563.9 1525.86  4572.1 1526.32  4592.1 1525.46  4918.0 1522.41  4960.1 1520.79
  4984.5 1517.68  5001.9 1516.43  5002.4 1515.93  5008.0 1516.43  5041.7 1517.85
  5107.0 1518.38  5122.6 1519.56  5132.1 1518.88  5150.5 1519.20  5222.1 1521.74
  5281.1 1525.11  5325.1 1529.43  5371.6 1536.01  5411.7 1538.05  5465.2 1539.49
#Mann=3,-1,0
  3989.4    0.07       0  5001.9    0.05       0  5008.0    0.07       0
Bank Sta=5001.9,5008
Exp/Cntr=0.3,0.1

Type RM Length L Ch R = 1,9664,451,451,451
BEGIN DESCRIPTION:
Bluff Creek 20.0
END DESCRIPTION:
XS GIS Cut Line= 4
      1969992.74     13897778.21      1969725.00     13896975.00
      1969625.00     13896675.00      1969325.03     13896475.02
#Sta/Elev= 30
  3837.6 1533.71  4301.0 1526.58  4332.6 1526.94  4380.0 1526.27  4402.1 1526.75
  4424.3 1525.37  4439.5 1525.71  4463.2 1523.68  4901.9 1519.11  4939.7 1518.07
  4966.0 1516.20  4973.1 1515.11  4985.0 1511.50  4987.2 1507.90  4987.7 1507.40
  4992.9 1507.40  4993.4 1507.90  5001.5 1507.98  5012.3 1514.74  5068.5 1513.64
  5077.2 1513.49  5109.6 1515.44  5222.8 1517.40  5239.4 1518.87  5250.2 1520.79
  5263.2 1525.34  5284.9 1530.56  5300.9 1532.48  5332.5 1535.14  5361.0 1536.49
#Mann=5,-1,0
  3837.6    0.07       0  4987.2    0.05       0  4993.4    0.07       0
  5068.5     0.1       0  5300.9    0.07       0
Bank Sta=4987.2,4993.4
Exp/Cntr=0.3,0.1

Type RM Length L Ch R = 1,9213,438,438,438
BEGIN DESCRIPTION:
Bluff Creek 19.0
END DESCRIPTION:
XS GIS Cut Line= 4
      1970436.55     13897069.76      1970058.89     13896616.06
      1969775.00     13896275.00      1969425.02     13896225.00
#Sta/Elev= 30
  3965.6 1525.13  3972.7 1524.96  4064.1 1523.62  4115.4 1520.65  4156.4 1522.72
  4211.8 1522.93  4220.3 1522.16  4258.6 1522.31  4299.4 1521.04  4369.1 1520.74
  4661.9 1516.81  4744.9 1514.97  4789.0 1513.19  4932.4 1512.29  4965.8 1511.15
  4987.1 1508.63  4993.4 1506.54  4994.9 1503.77  4995.4 1503.27  5001.3 1503.77
  5013.2 1506.10  5019.9 1509.25  5026.5 1509.86  5171.4 1514.84  5195.6 1517.15
  5220.1 1521.98  5247.1 1525.40  5295.6 1528.68  5318.2 1531.30  5353.2 1532.95
#Mann=5,-1,0
  3965.6    0.07       0  3972.7     0.1       0  4064.1    0.07       0
  4994.9    0.05       0  5001.3    0.07       0
Bank Sta=4994.9,5001.3
Exp/Cntr=0.3,0.1

Type RM Length L Ch R = 1,8775,451,451,451
BEGIN DESCRIPTION:
Bluff Creek 18.0
END DESCRIPTION:
XS GIS Cut Line= 4
      1970929.43     13896282.91      1970375.00     13896075.00
      1969975.00     13895925.00      1969575.03     13895925.00
#Sta/Elev= 30
  3975.7 1524.32  4195.1 1519.45  4210.0 1519.28  4220.7 1519.96  4288.0 1518.10
  4380.9 1517.08  4390.5 1516.09  4443.1 1516.21  4583.1 1514.11  4617.8 1514.29
  4641.1 1513.51  4807.0 1512.27  4874.3 1508.49  4893.6 1506.02  4925.6 1507.62
  4983.3 1506.73  4995.4 1505.24  5002.0 1503.46  5007.1 1500.34  5007.6 1499.84
  5013.6 1500.34  5023.0 1501.73  5032.0 1505.81  5037.4 1507.42  5053.0 1508.41
  5121.4 1508.14  5167.0 1508.80  5284.0 1512.59  5341.0 1515.23  5395.0 1521.93
#Mann=3,-1,0
  3975.7    0.07       0  5007.1    0.05       0  5013.6    0.07       0
Bank Sta=5007.1,5013.6
Exp/Cntr=0.3,0.1

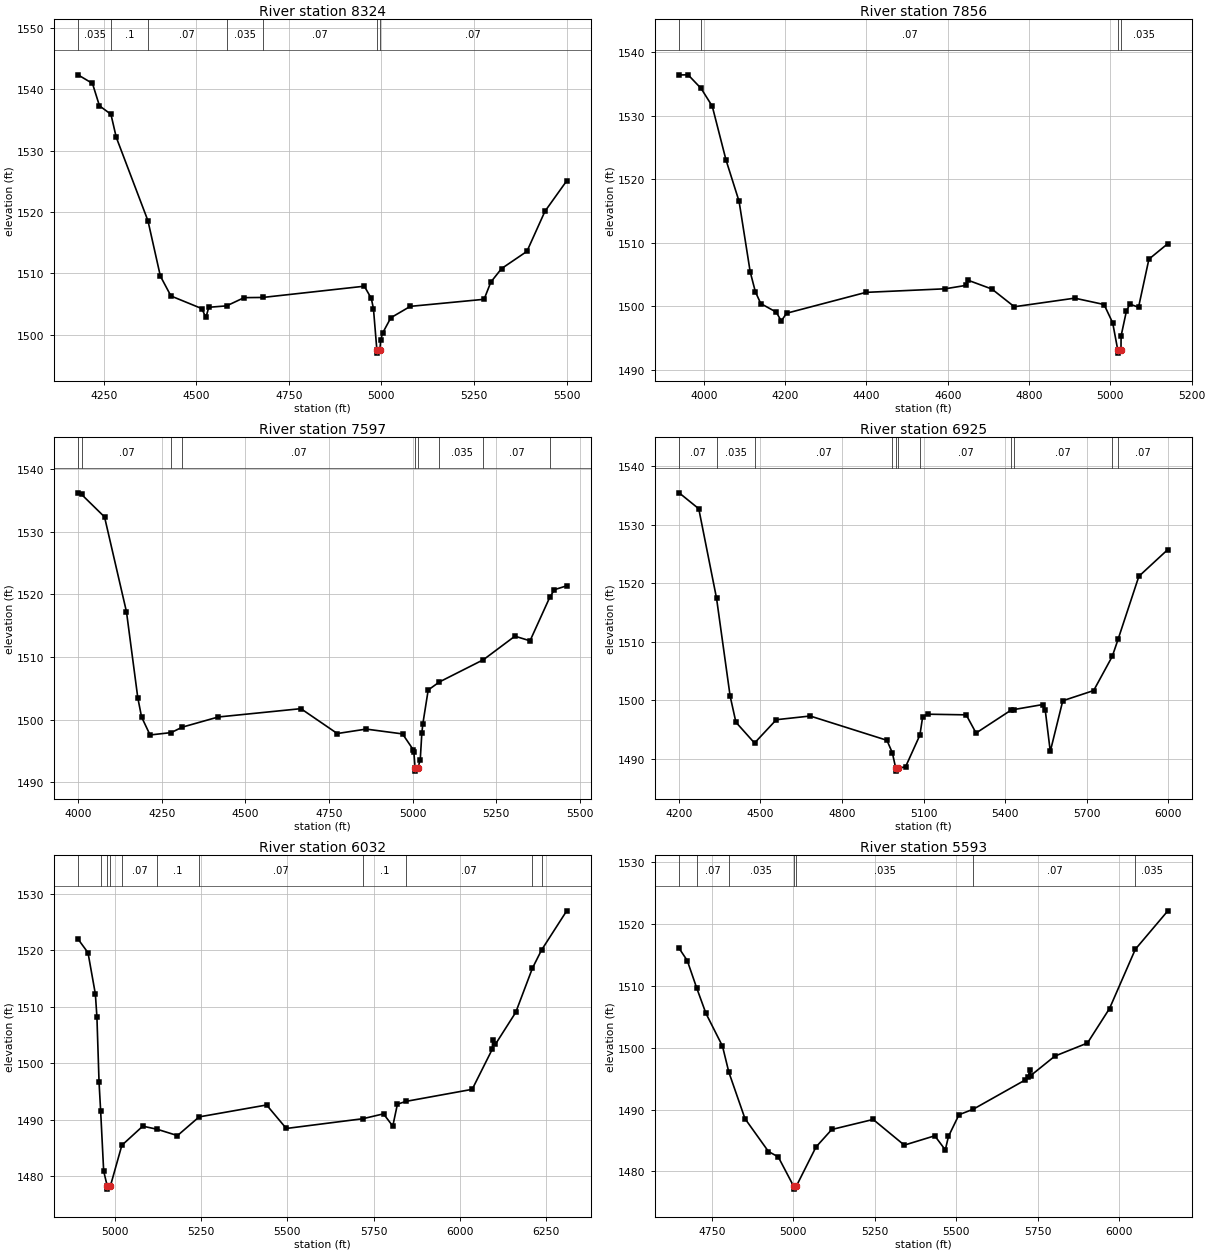
Type RM Length L Ch R = 1,8324,468,468,468
BEGIN DESCRIPTION:
Bluff Creek 17.0
END DESCRIPTION:
XS GIS Cut Line= 3
      1970575.00     13895025.00      1969925.00     13895525.00
      1969524.97     13895825.02
#Sta/Elev= 30
  4180.4 1542.32  4219.5 1540.92  4238.4 1537.28  4269.4 1535.90  4283.8 1532.15
  4369.4 1518.57  4402.9 1509.57  4431.5 1506.33  4514.7 1504.28  4525.9 1502.83
  4533.7 1504.49  4581.8 1504.72  4629.2 1506.06  4679.4 1506.09  4953.8 1507.92
  4972.7 1505.93  4978.5 1504.25  4987.7 1497.53  4988.2 1497.03  4995.6 1497.53
  4998.2 1499.17  5003.0 1500.27  5025.5 1502.79  5078.0 1504.64  5277.3 1505.79
  5295.5 1508.59  5324.5 1510.79  5393.0 1513.59  5441.7 1520.11  5500.5 1525.07
#Mann=7,-1,0
  4180.4   0.035       0  4269.4     0.1       0  4369.4    0.07       0
  4581.8   0.035       0  4679.4    0.07       0  4987.7    0.05       0
  4995.6    0.07       0
Bank Sta=4987.7,4995.6
Exp/Cntr=0.3,0.1

Type RM Length L Ch R = 1,7856,259,259,259
BEGIN DESCRIPTION:
Bluff Creek 16.0
END DESCRIPTION:
XS GIS Cut Line= 3
      1970274.98     13894575.02      1969525.00     13895325.00
      1969425.04     13895424.96
#Sta/Elev= 30
  3939.3 1536.39  3961.4 1536.41  3993.3 1534.28  4020.8 1531.48  4054.7 1523.01
  4086.8 1516.52  4114.1 1505.45  4126.8 1502.32  4140.1 1500.46  4178.3 1499.11
  4190.5 1497.72  4203.7 1498.94  4398.9 1502.22  4593.5 1502.78  4645.0 1503.32
  4648.9 1504.15  4708.6 1502.74  4763.7 1499.96  4912.2 1501.31  4984.4 1500.31
  5005.6 1497.43  5018.1 1493.17  5018.6 1492.67  5026.0 1493.17  5026.3 1495.37
  5039.5 1499.32  5048.0 1500.37  5069.2 1499.88  5094.7 1507.44  5141.3 1509.88
#Mann=4,-1,0
  3939.3     0.1       0  3993.3    0.07       0  5018.1    0.05       0
  5026.0   0.035       0
Bank Sta=5018.1,5026
Exp/Cntr=0.3,0.1

Type RM Length L Ch R = 1,7597,672,672,672
BEGIN DESCRIPTION:
Bluff Creek 15.0
END DESCRIPTION:
XS GIS Cut Line= 4
      1970225.03     13894524.98      1969424.96     13895125.26
      1969309.63     13895218.58      1969259.62     13895526.96
#Sta/Elev= 30
  3999.8 1536.22  4010.4 1535.97  4079.2 1532.37  4144.8 1517.22  4178.6 1503.51
  4189.9 1500.44  4215.3 1497.57  4278.3 1497.95  4311.6 1498.82  4419.1 1500.44
  4666.2 1501.77  4774.9 1497.80  4861.2 1498.51  4970.0 1497.74  5001.7 1495.24
  5003.9 1494.82  5007.5 1492.30  5008.0 1491.80  5015.5 1492.30  5022.9 1493.56
  5027.6 1497.81  5030.8 1499.39  5046.7 1504.75  5080.4 1506.04  5212.0 1509.59
  5305.9 1513.34  5351.1 1512.60  5409.9 1519.52  5424.0 1520.76  5460.8 1521.38
#Mann=9,-1,0
  3999.8     0.1       0  4010.4    0.07       0  4278.3   0.035       0
  4311.6    0.07       0  5007.5    0.05       0  5015.5    0.07       0
  5080.4   0.035       0  5212.0    0.07       0  5409.9   0.035       0
Bank Sta=5007.5,5015.5
Exp/Cntr=0.3,0.1

Type RM Length L Ch R = 1,6925,893,893,893
BEGIN DESCRIPTION:
Bluff Creek 14.0
END DESCRIPTION:
XS GIS Cut Line= 3
      1970114.46     13894400.63      1969325.00     13894525.00
      1968348.01     13894735.49
#Sta/Elev= 30
  4200.5 1535.48  4272.8 1532.76  4338.2 1517.47  4388.2 1500.75  4409.5 1496.27
  4478.0 1492.71  4558.3 1496.70  4682.8 1497.33  4965.3 1493.18  4985.2 1491.04
  4997.7 1488.41  4998.2 1487.91  5005.7 1488.41  5033.9 1488.65  5086.6 1494.07
  5096.9 1497.23  5115.3 1497.64  5257.0 1497.53  5293.3 1494.42  5423.5 1498.38
  5432.0 1498.43  5538.8 1499.29  5548.0 1498.29  5566.4 1491.27  5612.4 1499.94
  5726.0 1501.68  5794.5 1507.52  5815.9 1510.44  5892.4 1521.21  5999.1 1525.79
#Mann=11,-1,0
  4200.5    0.07       0  4338.2   0.035       0  4478.0    0.07       0
  4985.2     0.1       0  4997.7    0.05       0  5005.7     0.1       0
  5086.6    0.07       0  5423.5     0.1       0  5432.0    0.07       0
  5794.5     0.1       0  5815.9    0.07       0
Bank Sta=4997.7,5005.7
Exp/Cntr=0.3,0.1

Type RM Length L Ch R = 1,6032,439,439,439
BEGIN DESCRIPTION:
Bluff Creek 13.0
END DESCRIPTION:
XS GIS Cut Line= 3
      1969525.01     13893674.98      1969475.00     13893775.00
      1968308.13     13894360.83
#Sta/Elev= 30
  4892.7 1521.99  4921.8 1519.56  4943.1 1512.26  4947.6 1508.23  4953.8 1496.64
  4958.4 1491.59  4967.2 1480.90  4977.7 1478.20  4978.2 1477.70  4986.5 1478.20
  5019.9 1485.46  5080.6 1488.85  5123.0 1488.29  5181.3 1487.18  5244.0 1490.49
  5439.8 1492.60  5496.9 1488.44  5719.1 1490.17  5778.8 1491.03  5805.7 1488.86
  5819.1 1492.73  5843.2 1493.23  6036.0 1495.37  6094.4 1502.49  6095.2 1504.17
  6103.6 1503.37  6162.3 1509.00  6210.7 1516.82  6237.2 1520.04  6310.2 1526.98
#Mann=11,-1,0
  4892.7    0.07       0  4958.4     0.1       0  4977.7    0.05       0
  4986.5     0.1       0  5019.9    0.07       0  5123.0     0.1       0
  5244.0    0.07       0  5719.1     0.1       0  5843.2    0.07       0
  6210.7   0.035       0  6237.2    0.07       0
Bank Sta=4977.7,4986.5
Exp/Cntr=0.3,0.1

Type RM Length L Ch R = 1,5593,447,447,447
BEGIN DESCRIPTION:
Bluff Creek 12.0
END DESCRIPTION:
XS GIS Cut Line= 3
      1969524.98     13893475.00      1969175.00     13893475.00
      1968105.79     13893895.22
#Sta/Elev= 30
  4650.0 1516.06  4675.0 1514.08  4704.0 1509.64  4732.3 1505.54  4783.0 1500.25
  4802.5 1496.04  4852.0 1488.53  4924.0 1483.22  4954.0 1482.35  5000.9 1477.64
  5001.4 1477.14  5009.7 1477.64  5069.8 1483.95  5118.2 1486.78  5245.0 1488.40
  5340.6 1484.25  5434.0 1485.76  5466.3 1483.48  5476.0 1485.66  5508.2 1489.16
  5552.5 1490.07  5711.3 1494.78  5720.9 1495.19  5724.9 1496.41  5728.2 1495.49
  5802.3 1498.64  5902.2 1500.75  5969.9 1506.33  6049.1 1515.91  6148.8 1522.12
#Mann=7,-1,0
  4650.0   0.035       0  4704.0    0.07       0  4802.5   0.035       0
  5000.9   0.035       0  5009.7   0.035       0  5552.5    0.07       0
  6049.1   0.035       0
Bank Sta=5000.9,5009.7
Exp/Cntr=0.3,0.1

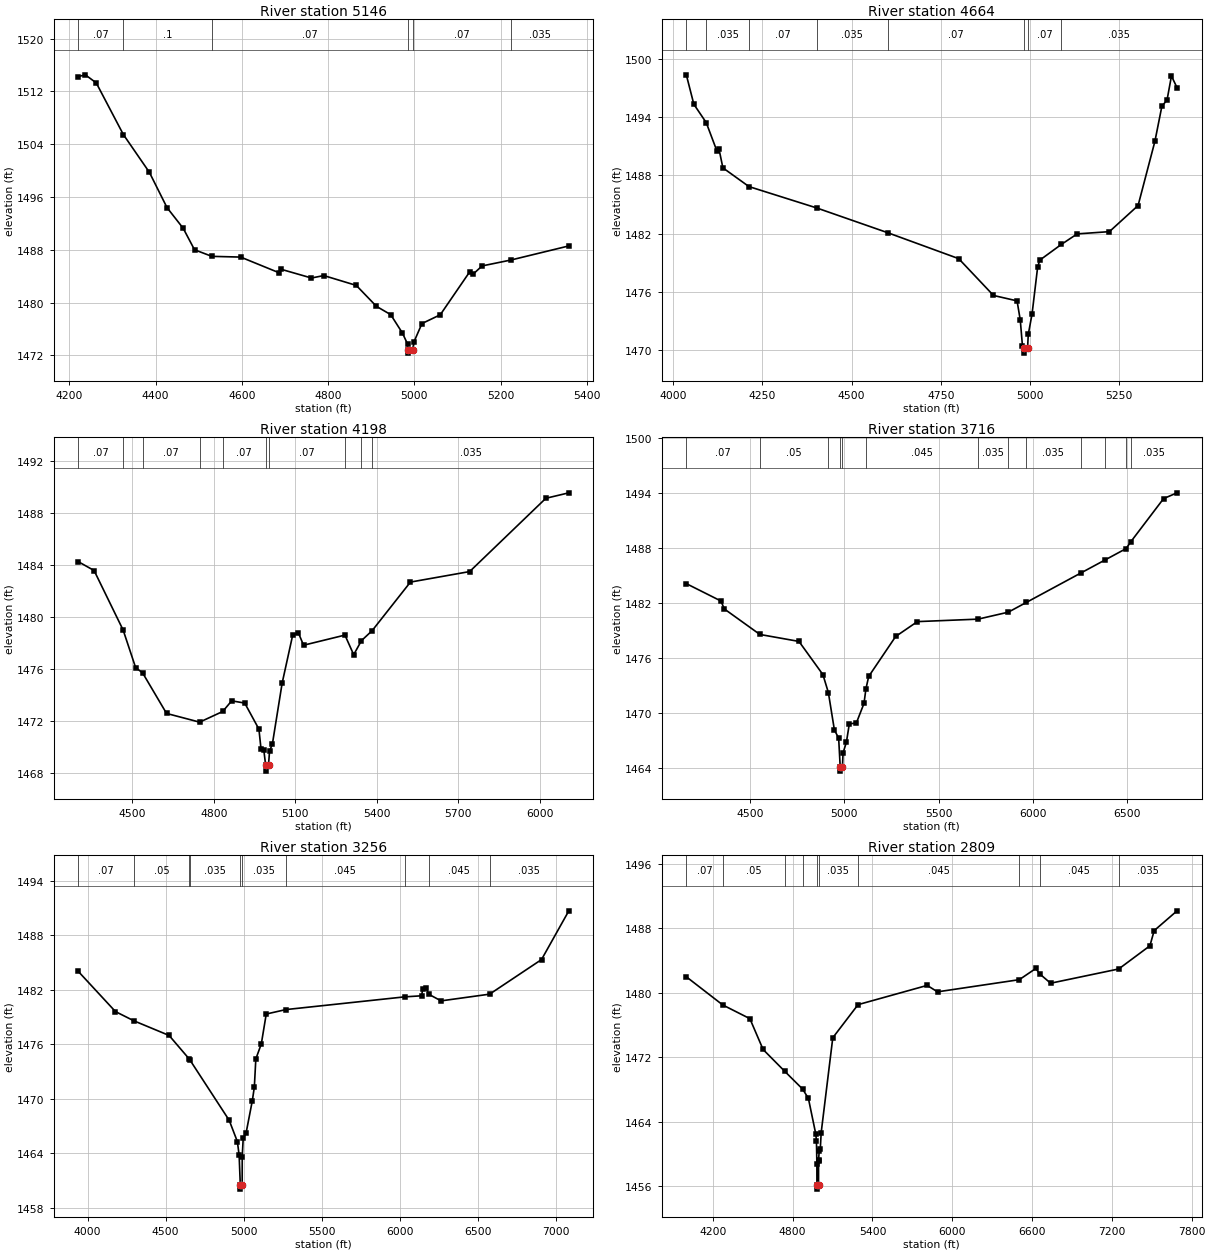
Type RM Length L Ch R = 1,5146,482,482,482
BEGIN DESCRIPTION:
Bluff Creek 11.0
END DESCRIPTION:
XS GIS Cut Line= 4
      1969675.01     13893325.00      1969031.84     13893114.69
      1968925.00     13893125.00      1968574.98     13893175.00
#Sta/Elev= 30
  4220.4 1514.24  4237.2 1514.51  4262.5 1513.29  4325.3 1505.47  4385.6 1499.75
  4426.6 1494.39  4464.1 1491.26  4490.3 1488.01  4530.5 1487.01  4597.3 1486.90
  4685.4 1484.55  4691.7 1485.04  4761.4 1483.73  4790.0 1484.10  4865.3 1482.61
  4912.0 1479.44  4945.1 1478.18  4972.3 1475.39  4984.3 1473.71  4984.9 1472.85
  4985.4 1472.35  4995.8 1472.85  4999.4 1474.11  5017.5 1476.83  5060.0 1478.16
  5128.7 1484.71  5135.7 1484.29  5156.9 1485.56  5224.1 1486.46  5358.0 1488.59
#Mann=6,-1,0
  4220.4    0.07       0  4325.3     0.1       0  4530.5    0.07       0
  4984.9    0.05       0  4995.8    0.07       0  5224.1   0.035       0
Bank Sta=4984.9,4995.8
Exp/Cntr=0.3,0.1

Type RM Length L Ch R = 1,4664,466,466,466
BEGIN DESCRIPTION:
Bluff Creek 10.0
END DESCRIPTION:
XS GIS Cut Line= 4
      1969625.02     13893175.02      1968955.89     13892680.90
      1968825.00     13892675.00      1968425.03     13892774.99
#Sta/Elev= 30
  4037.1 1498.35  4058.2 1495.32  4092.9 1493.43  4122.5 1490.54  4128.7 1490.70
  4139.6 1488.77  4212.7 1486.84  4402.5 1484.64  4601.5 1482.09  4800.3 1479.42
  4897.8 1475.63  4963.9 1475.07  4972.9 1473.09  4978.9 1470.47  4982.4 1470.19
  4982.9 1469.69  4993.3 1470.19  4995.3 1471.62  5005.9 1473.72  5021.6 1478.57
  5027.7 1479.27  5087.8 1480.88  5132.4 1481.97  5222.6 1482.20  5303.0 1484.89
  5350.1 1491.50  5369.7 1495.12  5384.1 1495.75  5396.5 1498.23  5412.2 1497.02
#Mann=8,-1,0
  4037.1    0.07       0  4092.9   0.035       0  4212.7    0.07       0
  4402.5   0.035       0  4601.5    0.07       0  4982.4    0.05       0
  4993.3    0.07       0  5087.8   0.035       0
Bank Sta=4982.4,4993.3
Exp/Cntr=0.3,0.1

Type RM Length L Ch R = 1,4198,482,482,482
BEGIN DESCRIPTION:
Bluff Creek 9.0
END DESCRIPTION:
XS GIS Cut Line= 4
      1969474.99     13892225.00      1968775.00     13892225.00
      1968663.31     13892228.74      1967704.91     13892501.88
#Sta/Elev= 30
  4299.6 1484.26  4358.6 1483.57  4465.8 1478.98  4511.6 1476.10  4537.4 1475.69
  4625.6 1472.57  4747.5 1471.90  4832.5 1472.72  4865.6 1473.54  4913.6 1473.37
  4966.0 1471.36  4973.6 1469.85  4984.0 1469.75  4990.5 1468.63  4991.0 1468.13
  5001.5 1468.63  5005.1 1469.67  5015.6 1470.22  5051.5 1474.90  5090.6 1478.62
  5111.7 1478.76  5130.4 1477.82  5282.9 1478.60  5315.2 1477.09  5343.6 1478.17
  5383.1 1478.94  5524.2 1482.68  5742.5 1483.49  6023.3 1489.13  6107.9 1489.55
#Mann=10,-1,0
  4299.6    0.07       0  4465.8    0.05       0  4537.4    0.07       0
  4747.5    0.05       0  4832.5    0.07       0  4990.5   0.045       0
  5001.5    0.07       0  5282.9   0.035       0  5343.6   0.045       0
  5383.1   0.035       0
Bank Sta=4990.5,5001.5
Exp/Cntr=0.3,0.1

Type RM Length L Ch R = 1,3716,460,460,460
BEGIN DESCRIPTION:
Bluff Creek 8.0
END DESCRIPTION:
XS GIS Cut Line= 4
      1969582.99     13892220.38      1968875.00     13891775.00
      1968272.64     13891611.71      1967190.39     13891966.00
#Sta/Elev= 30
  4163.6 1484.08  4346.7 1482.19  4365.0 1481.32  4553.2 1478.54  4760.3 1477.78
  4887.2 1474.16  4916.1 1472.20  4948.1 1468.11  4970.5 1467.25  4978.6 1464.14
  4979.1 1463.64  4990.7 1464.14  4993.8 1465.63  5011.4 1466.78  5027.0 1468.79
  5064.3 1468.89  5104.7 1471.02  5115.0 1472.61  5129.5 1473.96  5272.5 1478.32
  5387.5 1479.94  5708.9 1480.21  5869.1 1480.97  5964.5 1482.03  6251.6 1485.22
  6383.2 1486.68  6492.9 1487.90  6518.1 1488.65  6691.5 1493.35  6762.9 1493.98
#Mann=13,-1,0
  4163.6    0.07       0  4553.2    0.05       0  4916.1   0.035       0
  4978.6   0.035       0  4990.7   0.035       0  5115.0   0.045       0
  5708.9   0.035       0  5869.1   0.045       0  5964.5   0.035       0
  6251.6   0.045       0  6383.2   0.035       0  6492.9   0.045       0
  6518.1   0.035       0
Bank Sta=4978.6,4990.7
Exp/Cntr=0.3,0.1

Type RM Length L Ch R = 1,3256,447,447,447
BEGIN DESCRIPTION:
Bluff Creek 7.0
END DESCRIPTION:
XS GIS Cut Line= 5
      1969661.02     13892229.46      1969025.00     13891375.00
      1968925.00     13891275.00      1968447.24     13891117.20
      1967096.57     13891601.44
#Sta/Elev= 30
  3939.3 1484.06  4178.8 1479.61  4297.3 1478.59  4522.5 1476.98  4649.4 1474.43
  4656.3 1474.27  4907.7 1467.63  4960.1 1465.28  4971.3 1463.78  4978.7 1460.55
  4979.2 1460.05  4990.8 1460.55  4991.2 1463.64  4997.5 1465.68  5015.8 1466.23
  5055.9 1469.80  5068.7 1471.28  5078.3 1474.39  5113.4 1476.05  5145.0 1479.34
  5270.8 1479.83  6031.1 1481.23  6140.9 1481.35  6147.2 1482.10  6169.6 1482.21
  6186.3 1481.52  6265.2 1480.79  6576.5 1481.53  6908.9 1485.34  7083.9 1490.71
#Mann=10,-1,0
  3939.3    0.07       0  4297.3    0.05       0  4649.4    0.07       0
  4656.3   0.035       0  4978.7   0.035       0  4990.8   0.035       0
  5270.8   0.045       0  6031.1   0.035       0  6186.3   0.045       0
  6576.5   0.035       0
Bank Sta=4978.7,4990.8
Exp/Cntr=0.3,0.1

Type RM Length L Ch R = 1,2809,942,942,942
BEGIN DESCRIPTION:
Bluff Creek 6.0
END DESCRIPTION:
XS GIS Cut Line= 5
      1969765.31     13892169.26      1969425.00     13891225.00
      1969375.00     13891125.00      1968549.74     13890908.71
      1966924.70     13891476.44
#Sta/Elev= 30
  4000.4 1481.99  4274.5 1478.49  4478.3 1476.79  4577.8 1472.96  4741.7 1470.23
  4874.6 1468.05  4918.4 1466.89  4973.9 1462.46  4979.0 1461.59  4982.2 1458.79
  4982.5 1456.12  4983.0 1455.62  4994.6 1456.12  4994.8 1459.13  4994.9 1459.23
  4999.7 1460.35  5007.9 1460.62  5014.6 1462.65  5101.8 1474.42  5291.8 1478.53
  5811.6 1480.92  5889.2 1480.12  6504.0 1481.63  6628.4 1483.02  6656.9 1482.36
  6739.6 1481.19  7251.7 1482.96  7486.4 1485.84  7518.2 1487.72  7690.4 1490.18
#Mann=10,-1,0
  4000.4    0.07       0  4274.5    0.05       0  4741.7    0.07       0
  4874.6   0.035       0  4982.5   0.035       0  4994.6   0.035       0
  5291.8   0.045       0  6504.0   0.035       0  6656.9   0.045       0
  7251.7   0.035       0
Bank Sta=4982.5,4994.6
Exp/Cntr=0.3,0.1