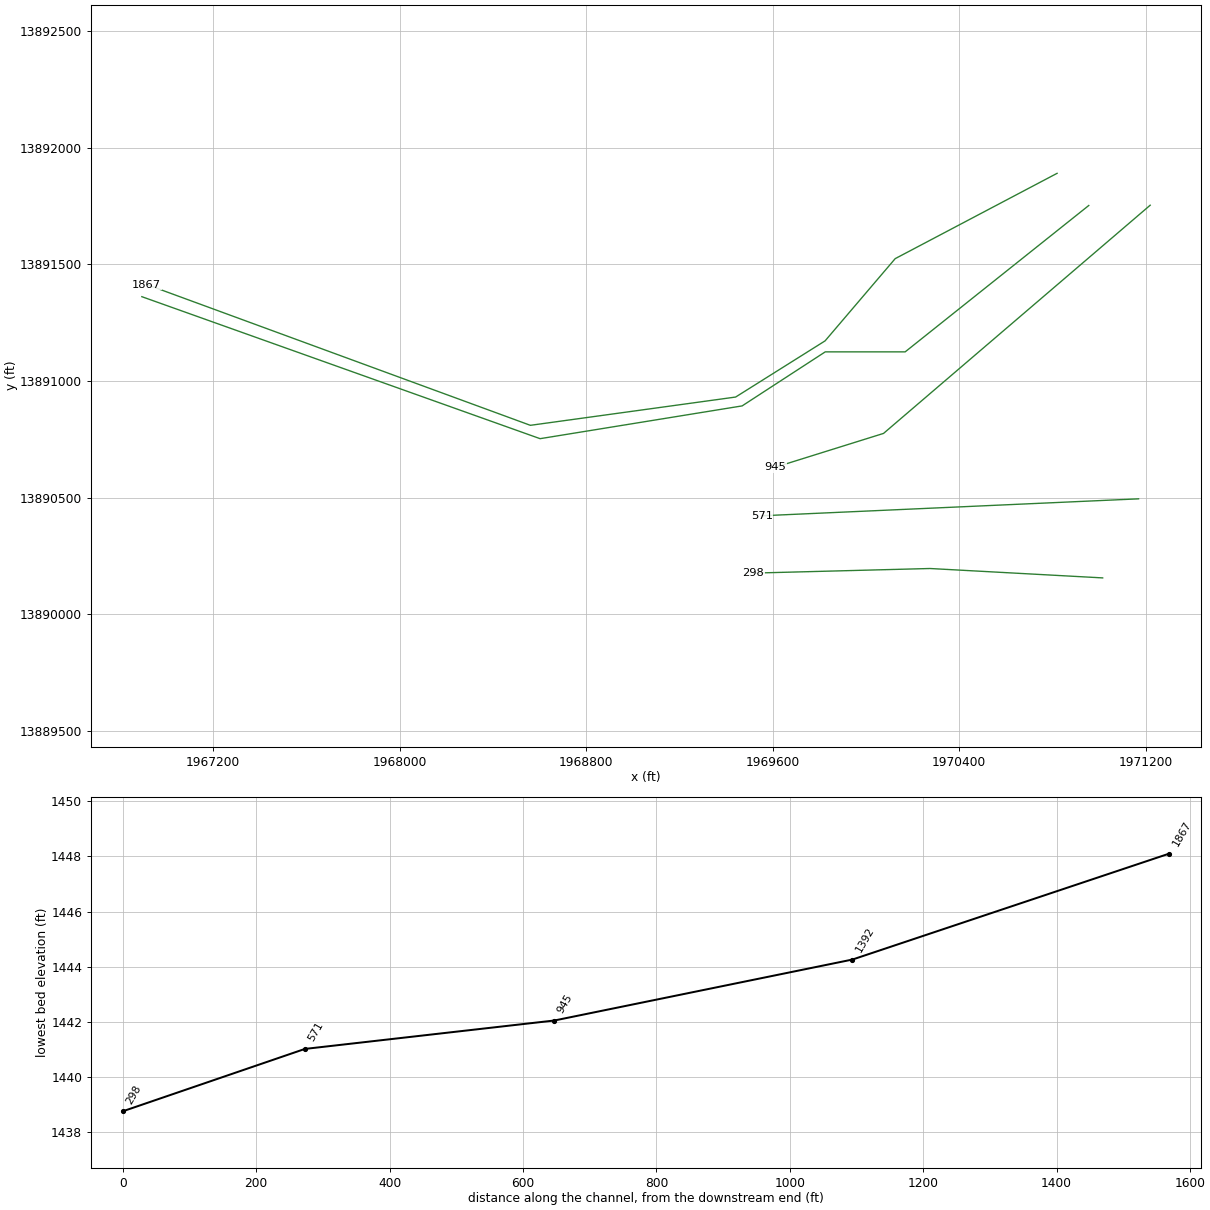
HEC-RAS study Bluff Creek.prj: Bluff Creek Base Level Engineering

--- Bluff Creek.g01 (geometry) --- (continued)

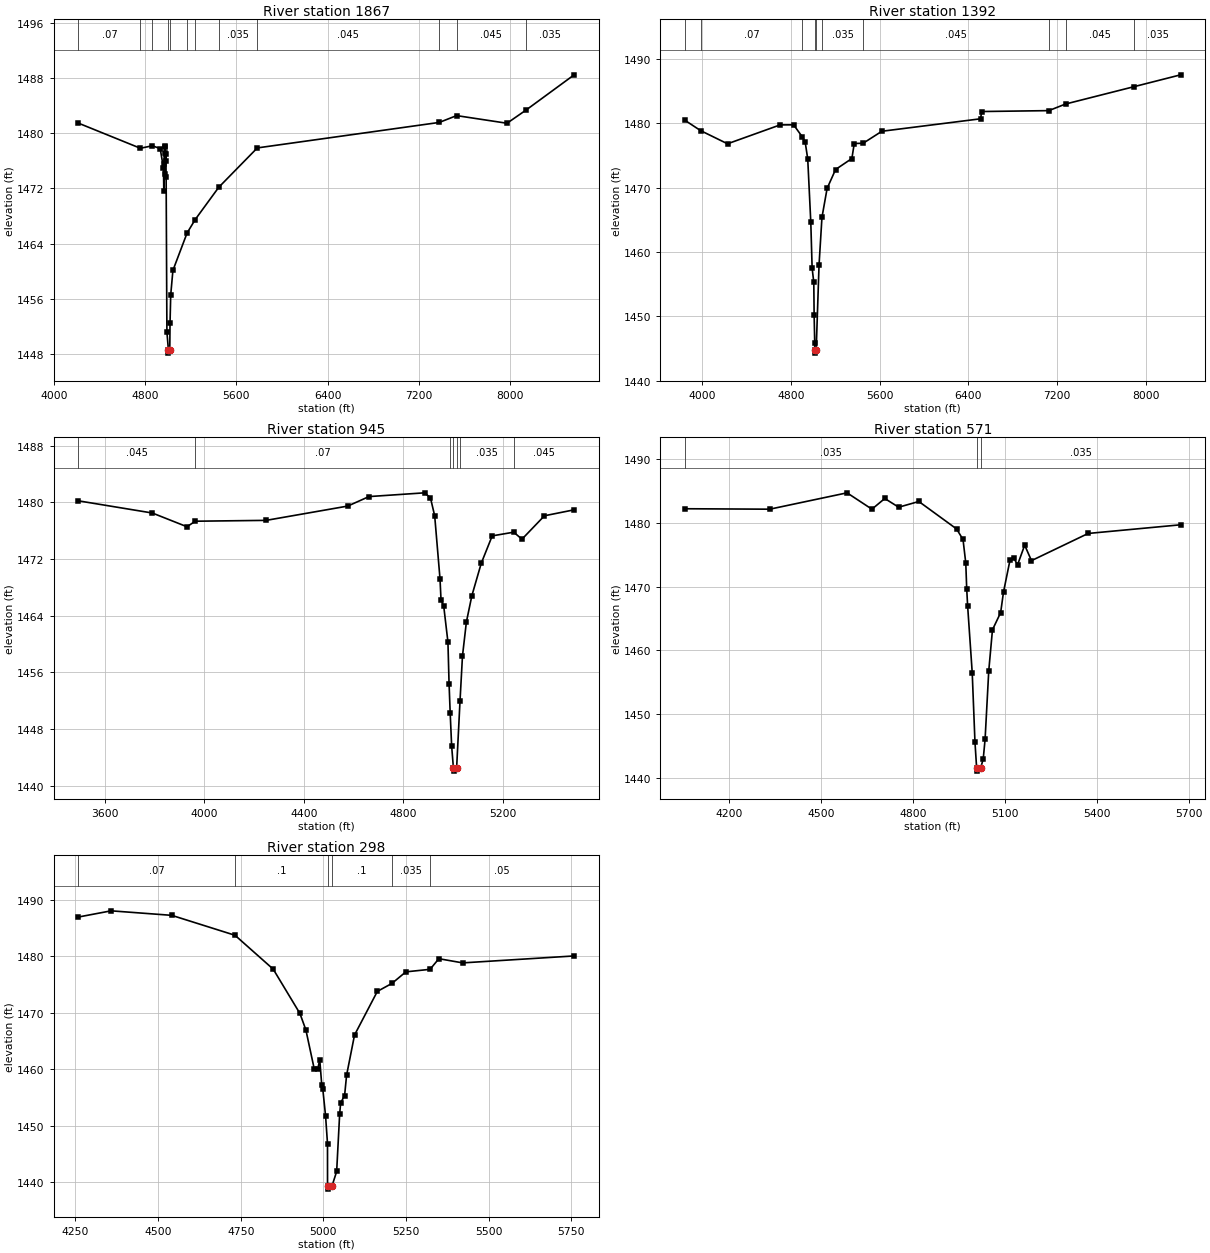
Type RM Length L Ch R = 1,1867,475,475,475
BEGIN DESCRIPTION:
Bluff Creek 4.0
END DESCRIPTION:
XS GIS Cut Line= 6
      1970819.55     13891891.21      1970125.00     13891525.00
      1969824.37     13891172.20      1969440.63     13890931.12
      1968560.16     13890809.76      1966914.36     13891413.91
#Sta/Elev= 30
  4214.9 1481.49  4758.6 1477.84  4863.3 1478.20  4932.2 1477.79  4961.1 1474.94
  4963.9 1471.58  4965.6 1475.53  4970.7 1477.13  4972.2 1474.17  4975.1 1478.01
  4977.5 1478.18  4978.9 1475.92  4981.6 1477.02  4984.2 1473.70  4991.0 1451.19
  5003.9 1448.60  5004.4 1448.10  5016.1 1448.60  5018.4 1452.48  5024.4 1456.55
  5043.5 1460.10  5167.8 1465.54  5238.9 1467.49  5445.5 1472.18  5783.1 1477.89
  7377.6 1481.59  7529.6 1482.58  7971.0 1481.47  8139.2 1483.40  8559.4 1488.50
#Mann=12,-1,0
  4214.9    0.07       0  4758.6   0.035       0  4863.3    0.07       0
  5003.9    0.05       0  5016.1    0.07       0  5167.8   0.035       0
  5238.9    0.07       0  5445.5   0.035       0  5783.1   0.045       0
  7377.6   0.035       0  7529.6   0.045       0  8139.2   0.035       0
Bank Sta=5003.9,5016.1
Exp/Cntr=0.3,0.1

Type RM Length L Ch R = 1,1392,447,447,447
BEGIN DESCRIPTION:
Bluff Creek 3.0
END DESCRIPTION:
XS GIS Cut Line= 6
      1970955.43     13891753.15      1970167.83     13891125.00
      1969825.00     13891125.00      1969468.55     13890893.11
      1968601.82     13890752.46      1966893.50     13891361.84
#Sta/Elev= 30
  3845.4 1480.50  3987.8 1478.88  4230.3 1476.83  4704.2 1479.77  4825.9 1479.78
  4903.1 1477.93  4929.6 1477.14  4953.0 1474.48  4980.6 1464.62  4992.6 1457.48
  5007.6 1455.28  5010.6 1450.23  5016.0 1445.87  5016.1 1444.76  5016.6 1444.26
  5029.2 1444.76  5055.0 1458.01  5081.1 1465.37  5127.6 1469.89  5204.0 1472.83
  5350.7 1474.54  5372.2 1476.87  5452.7 1476.92  5620.9 1478.78  6510.4 1480.72
  6520.0 1481.85  7125.1 1481.99  7276.3 1483.02  7895.9 1485.73  8312.7 1487.56
#Mann=10,-1,0
  3845.4   0.045       0  3987.8    0.07       0  4903.1     0.1       0
  5016.1    0.05       0  5029.2     0.1       0  5081.1   0.035       0
  5452.7   0.045       0  7125.1   0.035       0  7276.3   0.045       0
  7895.9   0.035       0
Bank Sta=5016.1,5029.2
Exp/Cntr=0.3,0.1

Type RM Length L Ch R = 1,945,374,374,374
BEGIN DESCRIPTION:
Bluff Creek 2.0
END DESCRIPTION:
XS GIS Cut Line= 3
      1971218.94     13891754.40      1970075.00     13890775.00
      1969611.92     13890630.26
#Sta/Elev= 30
  3494.3 1480.23  3791.3 1478.51  3930.6 1476.57  3963.8 1477.35  4248.5 1477.47
  4576.3 1479.49  4661.5 1480.83  4884.9 1481.36  4908.3 1480.65  4925.3 1478.12
  4946.6 1469.25  4950.8 1466.22  4961.5 1465.39  4978.5 1460.29  4983.1 1454.37
  4987.6 1450.24  4993.4 1445.60  5000.4 1442.55  5000.9 1442.05  5013.5 1442.55
  5027.0 1451.94  5036.9 1458.31  5052.6 1463.11  5074.6 1466.83  5112.3 1471.41
  5156.3 1475.28  5242.7 1475.80  5275.8 1474.81  5366.1 1478.12  5485.4 1478.96
#Mann=7,-1,0
  3494.3   0.045       0  3963.8    0.07       0  4987.6     0.1       0
  5000.4    0.05       0  5013.5     0.1       0  5027.0   0.035       0
  5242.7   0.045       0
Bank Sta=5000.4,5013.5
Exp/Cntr=0.3,0.1

Type RM Length L Ch R = 1,571,273,273,273
BEGIN DESCRIPTION:
Mapping XS bb67a909
END DESCRIPTION:
XS GIS Cut Line= 2
      1971168.95     13890494.24      1969552.58     13890421.54
#Sta/Elev= 30
  4055.2 1482.23  4332.4 1482.16  4584.7 1484.73  4665.8 1482.16  4707.8 1483.84
  4753.1 1482.47  4818.9 1483.37  4942.0 1479.06  4963.1 1477.40  4972.1 1473.70
  4975.1 1469.70  4978.1 1467.01  4993.1 1456.50  5002.1 1445.58  5007.5 1441.52
  5008.0 1441.02  5020.7 1441.52  5029.1 1442.95  5035.1 1446.01  5047.1 1456.79
  5059.2 1463.22  5085.9 1465.92  5095.2 1469.15  5116.2 1474.11  5128.2 1474.54
  5141.1 1473.42  5164.3 1476.51  5186.5 1474.08  5371.5 1478.35  5673.2 1479.71
#Mann=3,-1,0
  4055.2   0.035       0  5007.5   0.035       0  5020.7   0.035       0
Bank Sta=5007.5,5020.7
Exp/Cntr=0.3,0.1

Type RM Length L Ch R = 1,298,0,0,0
BEGIN DESCRIPTION:
Bluff Creek 1.0
END DESCRIPTION:
XS GIS Cut Line= 3
      1971015.08     13890154.97      1970274.24     13890195.28
      1969517.03     13890175.59
#Sta/Elev= 30
  4259.0 1486.95  4358.2 1488.05  4541.5 1487.25  4732.8 1483.72  4848.3 1477.72
  4929.1 1469.87  4947.1 1466.96  4972.2 1460.10  4983.1 1460.10  4989.1 1461.64
  4995.2 1457.14  4998.2 1456.53  5006.7 1451.70  5012.5 1446.81  5012.6 1439.26
  5013.1 1438.76  5025.8 1439.26  5040.2 1441.89  5049.2 1451.99  5052.2 1454.03
  5064.2 1455.33  5070.2 1458.92  5094.2 1466.05  5163.2 1473.78  5207.5 1475.20
  5249.4 1477.24  5322.6 1477.69  5349.3 1479.57  5421.3 1478.83  5758.4 1480.06
#Mann=6,-1,0
  4259.0    0.07       0  4732.8     0.1       0  5012.6    0.05       0
  5025.8     0.1       0  5207.5   0.035       0  5322.6    0.05       0
Bank Sta=5012.6,5025.8
Exp/Cntr=0.3,0.1

Chan Stop Cuts=-1