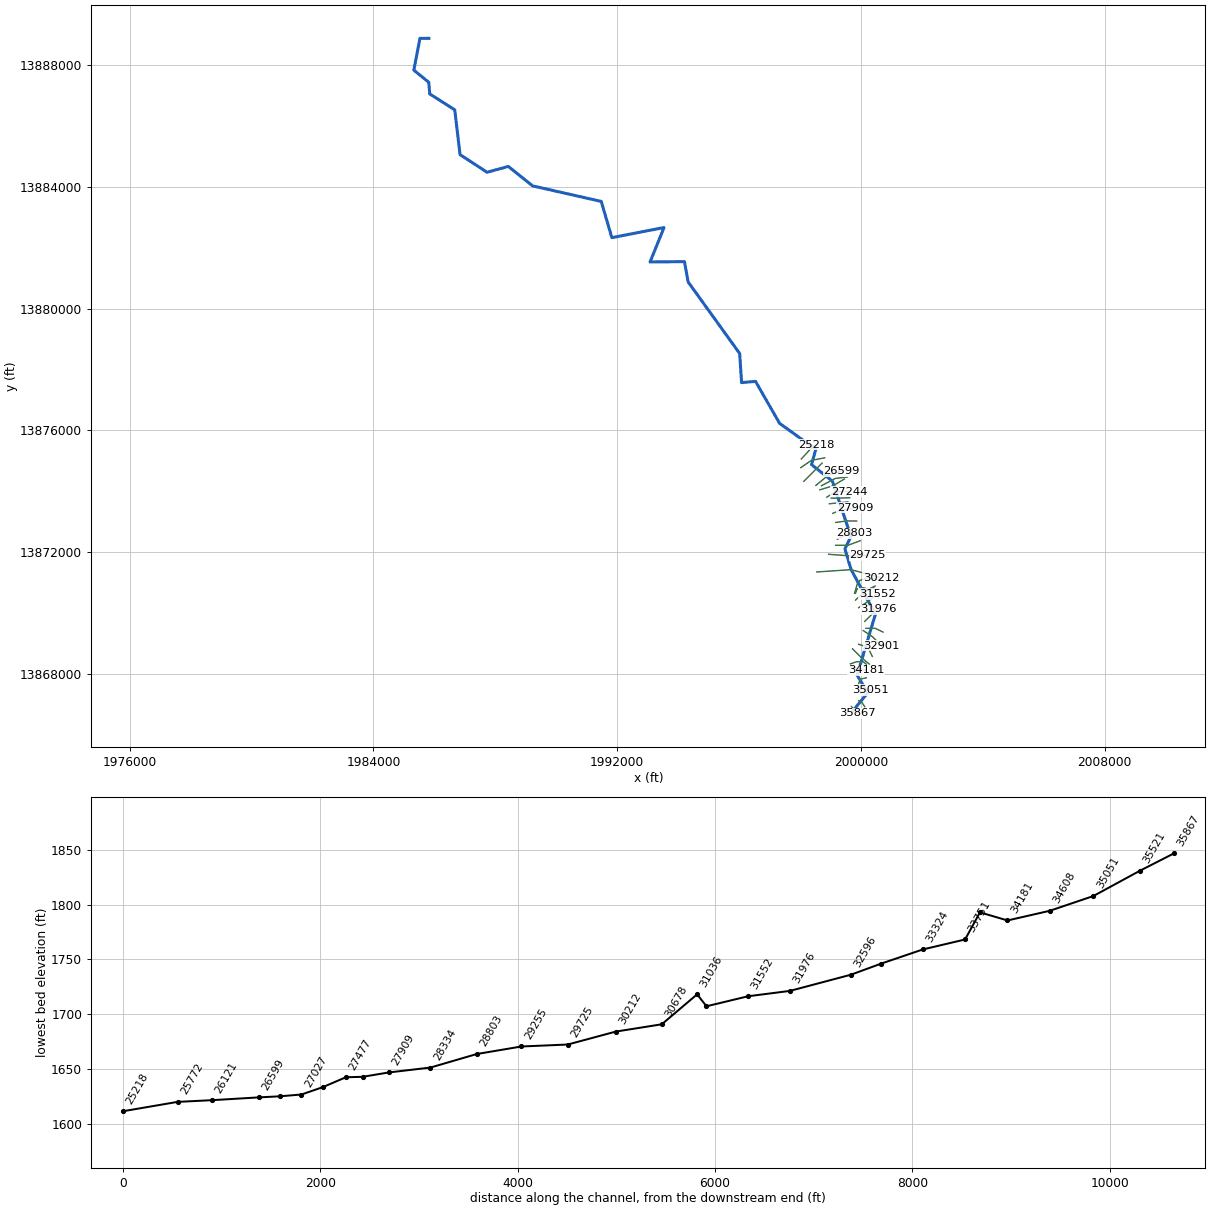
--- Bruins Creek.prj (project) ---

Proj Title=Bruins Creek Base Level Engineering
Current Plan=p01
Default Exp/Contr=0.3,0.1
English Units
Geom File=g01
Flow File=f01
Plan File=p01
Y Axis Title=Elevation
X Axis Title(PF)=Main Channel Distance
X Axis Title(XS)=Station
BEGIN DESCRIPTION:
Bruins Creek
END DESCRIPTION:
DSS Export Rating Curves= 0
DSS Export Rating Curve Sorted= 0
DSS Export Volume Flow Curves= 0
DXF OffsetX= 0
DXF OffsetY= 0
DXF ScaleX= 1
DXF ScaleY= 10

--- Bruins Creek.p01 (plan) ---

Plan Title=Multiple Run
Short Identifier=Multiple
Geom File=g01
Flow File=f01
Subcritical Flow
K Sum by GR= 0
Std Step Tol= 0.01
Critical Tol= 0.01
Num of Std Step Trials= 20
Max Error Tol= 0.3
Flow Tol Ratio= 0.001
Split Flow NTrial= 30
Split Flow Tol= 0.02
Split Flow Ratio= 0.02
Log Output Level= 0
Friction Slope Method= 1
Unsteady Friction Slope Method= 2
Unsteady Bridges Friction Slope Method= 1
Parabolic Critical Depth
Global Vel Dist=  1 , 1 , 1
Global Log Level= 0
CheckData=True
Encroach Param= -1, 0, 0, 0
BEGIN DESCRIPTION:
Multiple Run
END DESCRIPTION:

--- Bruins Creek.f01 (steady flow) ---

Flow Title=Multiple
Program Version=4.10
Number of Profiles= 7
Profile Names=10-year,25-year,50-year,1pct_min,100-year,1pct_plu,500-year
River Rch & RM=Bruins Creek,Reach-1         ,35867
     187     282     364     230     459     916     715
River Rch & RM=Bruins Creek,Reach-1         ,34608
     681    1137    1565    1048    2091    4172    3686
River Rch & RM=Bruins Creek,Reach-1         ,30212
    1399    2438    3455    2373    4734    9446    8800
River Rch & RM=Bruins Creek,Reach-1         ,29725
    1498    2620    3721    2560    5109   10193    9532
River Rch & RM=Bruins Creek,Reach-1         ,29255
    1635    2869    4082    2813    5612   11198   10504
River Rch & RM=Bruins Creek,Reach-1         ,27027
    2013    3561    5094    3525    7034   14034   13283
River Rch & RM=Bruins Creek,Reach-1         ,23346
    3456    6259    9094    6379   12728   25396   24710
River Rch & RM=Bruins Creek,Reach-1         ,17589
    3561    6449    9370    6571   13110   26159   25442
River Rch & RM=Bruins Creek,Reach-1         ,15269
    3783    6851    9951    6974   13916   27765   26973
River Rch & RM=Bruins Creek,Reach-1         ,9756
    4059    7365   10711    7513   14991   29911   29111
River Rch & RM=Bruins Creek,Reach-1         ,6960
    5350    9820   14395   10171   20294   40491   39982
River Rch & RM=Bruins Creek,Reach-1         ,5552
    5337    9779   14318   10103   20157   40219   39606
River Rch & RM=Bruins Creek,Reach-1         ,2603
    5434    9953   14566   10273   20497   40898   40232
Boundary for River Rch & Prof#=Bruins Creek,Reach-1         , 1
Up Type= 0
Dn Type= 3
Dn Slope=0.008
Boundary for River Rch & Prof#=Bruins Creek,Reach-1         , 2
Up Type= 0
Dn Type= 3
Dn Slope=0.008
Boundary for River Rch & Prof#=Bruins Creek,Reach-1         , 3
Up Type= 0
Dn Type= 3
Dn Slope=0.008
Boundary for River Rch & Prof#=Bruins Creek,Reach-1         , 4
Up Type= 0
Dn Type= 3
Dn Slope=0.008
Boundary for River Rch & Prof#=Bruins Creek,Reach-1         , 5
Up Type= 0
Dn Type= 3
Dn Slope=0.008
Boundary for River Rch & Prof#=Bruins Creek,Reach-1         , 6
Up Type= 0
Dn Type= 3
Dn Slope=0.008
Boundary for River Rch & Prof#=Bruins Creek,Reach-1         , 7
Up Type= 0
Dn Type= 3
Dn Slope=0.008
DSS Import GetInterval= 0
DSS Import GetPeak= 0
DSS Import FillOption= 0

--- Bruins Creek.g01 (geometry) ---

Geom Title=Existing Conditions
Program Version=4.10

River Reach=Bruins Creek    ,Reach-1
Reach XY= 30
        1999725.       13866775.      2000223.03     13867380.89
       1999874.9     13867959.64      2000474.91      13869959.6
      1999678.28     13871426.36       1999474.5     13872106.04
      1999673.81      13872514.5      1999065.42     13874331.55
      1998378.53     13874876.46       1998519.6     13875377.43
      1997330.26     13876230.47      1996541.76     13877608.57
      1996083.02     13877568.62      1996021.25     13878523.45
      1994330.73     13880872.45      1994208.55     13881542.14
      1993079.63     13881529.63      1993538.24     13882661.39
      1991826.58     13882328.67       1991477.3     13883519.17
      1989226.46     13884028.54      1988428.41     13884667.23
      1987730.94     13884477.25      1986844.59      13885054.8
      1986669.59     13886527.71      1985849.11     13887049.71
      1985817.19     13887431.82      1985326.96     13887830.88
      1985528.45     13888873.98        1985825.       13888875.

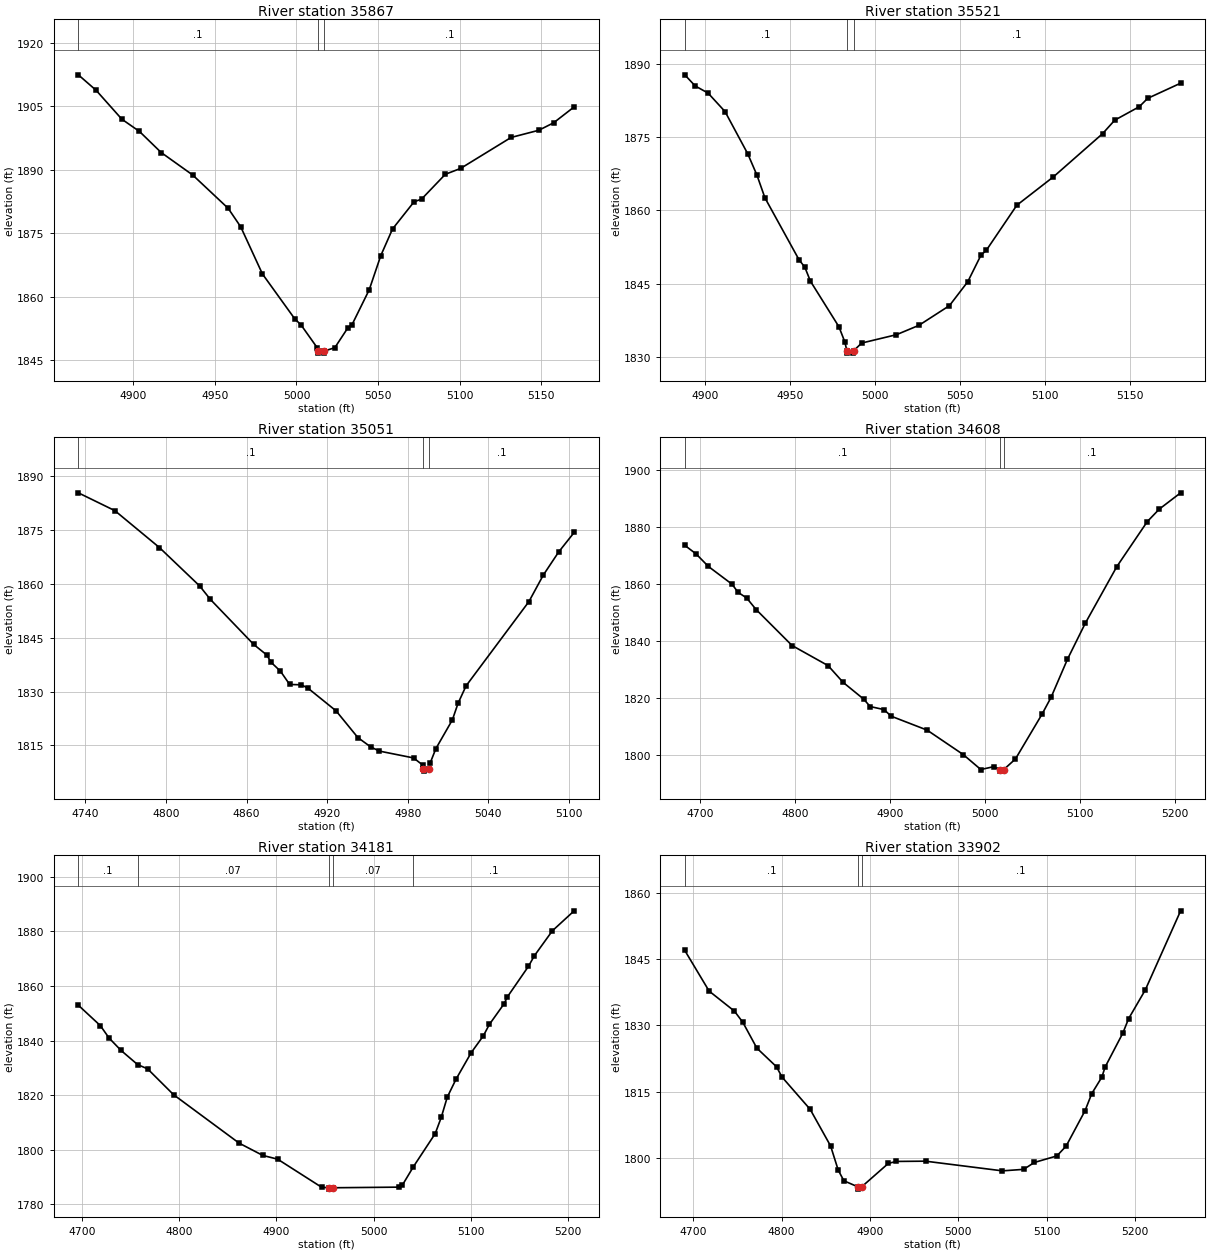
Type RM Length L Ch R = 1 ,35867   ,346,346,346
BEGIN DESCRIPTION:
Bruins Creek 76.0
END DESCRIPTION:
XS GIS Cut Line= 2
      1999689.86     13866928.91      1999895.58     13866704.95
#Sta/Elev= 30
  4866.2 1912.44  4877.1 1908.79  4892.9 1901.96  4903.7 1899.07    4917  1894.1
  4936.3  1888.8  4958.1 1880.92  4965.8 1876.55  4979.1 1865.43  4998.8  1854.9
  5002.9 1853.33  5012.7 1848.01  5013.1 1847.23  5013.3 1846.73  5016.8 1846.73
  5017.1 1847.23  5023.5 1848.01  5031.4 1852.64    5034  1853.4  5044.6 1861.68
  5051.7 1869.75  5058.9 1876.04  5072.1 1882.46  5076.7 1883.09  5091.3 1888.96
  5100.6 1890.33  5131.6 1897.65  5148.6 1899.35  5157.7 1901.11  5170.3 1904.87
#Mann= 3 ,-1 , 0
  4866.2      .1       0  5013.1     .05       0  5017.1      .1       0
Bank Sta=5013.1,5017.1
XS Rating Curve= 0 ,0
Exp/Cntr=0.3,0.1

Type RM Length L Ch R = 1 ,35521   ,470,470,470
BEGIN DESCRIPTION:
Bruins Creek 75.0
END DESCRIPTION:
XS GIS Cut Line= 3
      1999925.02     13867124.99        2000025.       13867075.
      2000125.03     13866924.96
#Sta/Elev= 30
    4888 1887.74  4894.1 1885.47  4901.7 1884.01  4911.7 1880.23  4925.1 1871.58
  4930.5 1867.23  4935.2 1862.59  4955.3 1849.92  4958.7 1848.41    4962 1845.55
  4978.8 1836.22  4982.2 1833.19  4983.5 1831.33  4983.8 1830.83  4987.3 1830.83
  4987.5 1831.33  4992.2 1832.89  5012.7  1834.6  5025.9 1836.51  5043.9 1840.54
  5054.7 1845.43  5062.5 1850.88  5065.6 1851.84  5083.6 1861.07  5105.2 1866.89
  5134.1  1875.7  5141.3 1878.47  5155.7 1881.21  5160.7 1882.93  5180.1 1886.03
#Mann= 3 ,-1 , 0
    4888      .1       0  4983.5     .05       0  4987.5      .1       0
Bank Sta=4983.5,4987.5
XS Rating Curve= 0 ,0
Exp/Cntr=0.3,0.1

Type RM Length L Ch R = 1 ,35051   ,443,443,443
BEGIN DESCRIPTION:
Bruins Creek 74.0
END DESCRIPTION:
XS GIS Cut Line= 3
      1999974.96     13867374.98        2000225.       13867475.
      2000324.99       13867475.
#Sta/Elev= 30
  4734.7 1885.29  4761.9 1880.33  4795.1 1870.06  4825.1 1859.36    4833 1855.65
  4865.3  1843.1    4875 1840.18  4878.3 1838.11  4885.2 1835.67  4892.1 1831.96
  4900.9 1831.86  4905.9 1830.88  4926.7  1824.6  4942.9 1817.18  4952.6 1814.54
    4959 1813.41  4984.4 1811.51  4991.4 1809.47  4991.6 1808.34  4991.9 1807.84
  4995.6 1808.34  4996.8 1810.14    5001  1814.1  5013.3 1822.11  5017.5 1826.69
  5023.5 1831.57  5070.3 1855.02    5081 1862.39  5092.5 1868.85    5104 1874.26
#Mann= 3 ,-1 , 0
  4734.7      .1       0  4991.6     .05       0  4995.6      .1       0
Bank Sta=4991.6,4995.6
XS Rating Curve= 0 ,0
Exp/Cntr=0.3,0.1

Type RM Length L Ch R = 1 ,34608   ,427,427,427
BEGIN DESCRIPTION:
Bruins Creek 73.0
END DESCRIPTION:
XS GIS Cut Line= 3
        1999875.     13867525.01        1999975.       13867825.
      2000175.03     13867875.01
#Sta/Elev= 30
  4683.8 1873.61  4695.7  1870.6  4708.7 1866.19  4733.6 1859.96  4739.9 1857.13
    4749 1855.12  4758.9 1851.09  4796.8 1838.45  4834.8 1831.38  4850.6 1825.51
  4872.3 1819.62  4879.1 1817.02  4893.7 1815.95  4901.2 1813.64  4939.1 1808.75
  4977.1 1800.18  4995.7 1794.91  5009.3 1795.92  5015.7 1794.85    5016 1794.35
  5019.7 1794.85  5032.2 1798.63  5060.1 1814.29  5069.7 1820.25    5087 1833.65
  5105.8  1846.3    5139 1866.16  5171.1 1881.96  5183.7 1886.33  5206.2 1892.05
#Mann= 3 ,-1 , 0
  4683.8      .1       0  5015.7     .05       0  5019.7      .1       0
Bank Sta=5015.7,5019.7
XS Rating Curve= 0 ,0
Exp/Cntr=0.3,0.1

Type RM Length L Ch R = 1 ,34181   ,279,279,279
BEGIN DESCRIPTION:
Bruins Creek 72.0
END DESCRIPTION:
XS GIS Cut Line= 3
      1999674.97     13868225.01        1999975.       13868175.
      2000174.98     13868125.01
#Sta/Elev= 30
  4696.1 1852.95  4718.7 1845.49  4727.8  1840.9    4740  1836.4  4757.1  1831.2
  4767.4 1829.63  4794.1 1820.17  4861.6 1802.42    4886 1797.91  4901.2 1796.55
  4946.4 1786.28  4953.9 1786.07  4954.2 1785.57  4957.9 1786.07  5026.3  1786.3
  5029.4 1786.92    5041 1793.81  5063.4 1805.92  5069.6 1811.84  5075.8 1819.26
  5084.8 1825.83  5100.5  1835.6  5112.9 1841.71  5119.1 1845.89  5134.3 1853.48
  5137.6 1855.96  5159.3 1867.16  5165.5 1871.09    5184 1880.22  5206.4 1887.53
#Mann= 5 ,-1 , 0
  4696.1      .1       0  4757.1     .07       0  4953.9     .05       0
  4957.9     .07       0    5041      .1       0
Bank Sta=4953.9,4957.9
XS Rating Curve= 0 ,0
Exp/Cntr=0.3,0.1

Type RM Length L Ch R = 1 ,33902   ,151,151,151
BEGIN DESCRIPTION:
Mapping XS 7a73be92
END DESCRIPTION:
XS GIS Cut Line= 4
      1999653.28     13868330.47        1999862.      13868402.8
      2000076.85     13868398.46      2000176.03     13868322.53
#Sta/Elev= 30
  4690.6 1846.91  4718.1 1837.73  4746.7  1833.2  4756.2 1830.68  4772.1 1824.83
  4794.3 1820.62  4800.6 1818.28  4832.4 1810.99  4855.5 1802.71  4864.1 1797.25
  4870.5 1794.85  4886.5 1793.46  4886.7 1792.96  4890.5 1793.46  4920.8 1798.78
  4929.8 1799.22  4962.8 1799.28  5049.8 1797.09  5073.8 1797.43  5085.8 1798.98
  5111.3 1800.46  5121.8 1802.68  5143.2 1810.68  5150.8 1814.55  5162.2 1818.27
  5165.9 1820.55    5186 1828.25  5192.5  1831.5  5211.3 1837.97  5251.3 1855.87
#Mann= 3 ,-1 , 0
  4690.6      .1       0  4886.5     .05       0  4890.5      .1       0
Bank Sta=4886.5,4890.5
XS Rating Curve= 0 ,0
Exp/Cntr=0.3,0.1

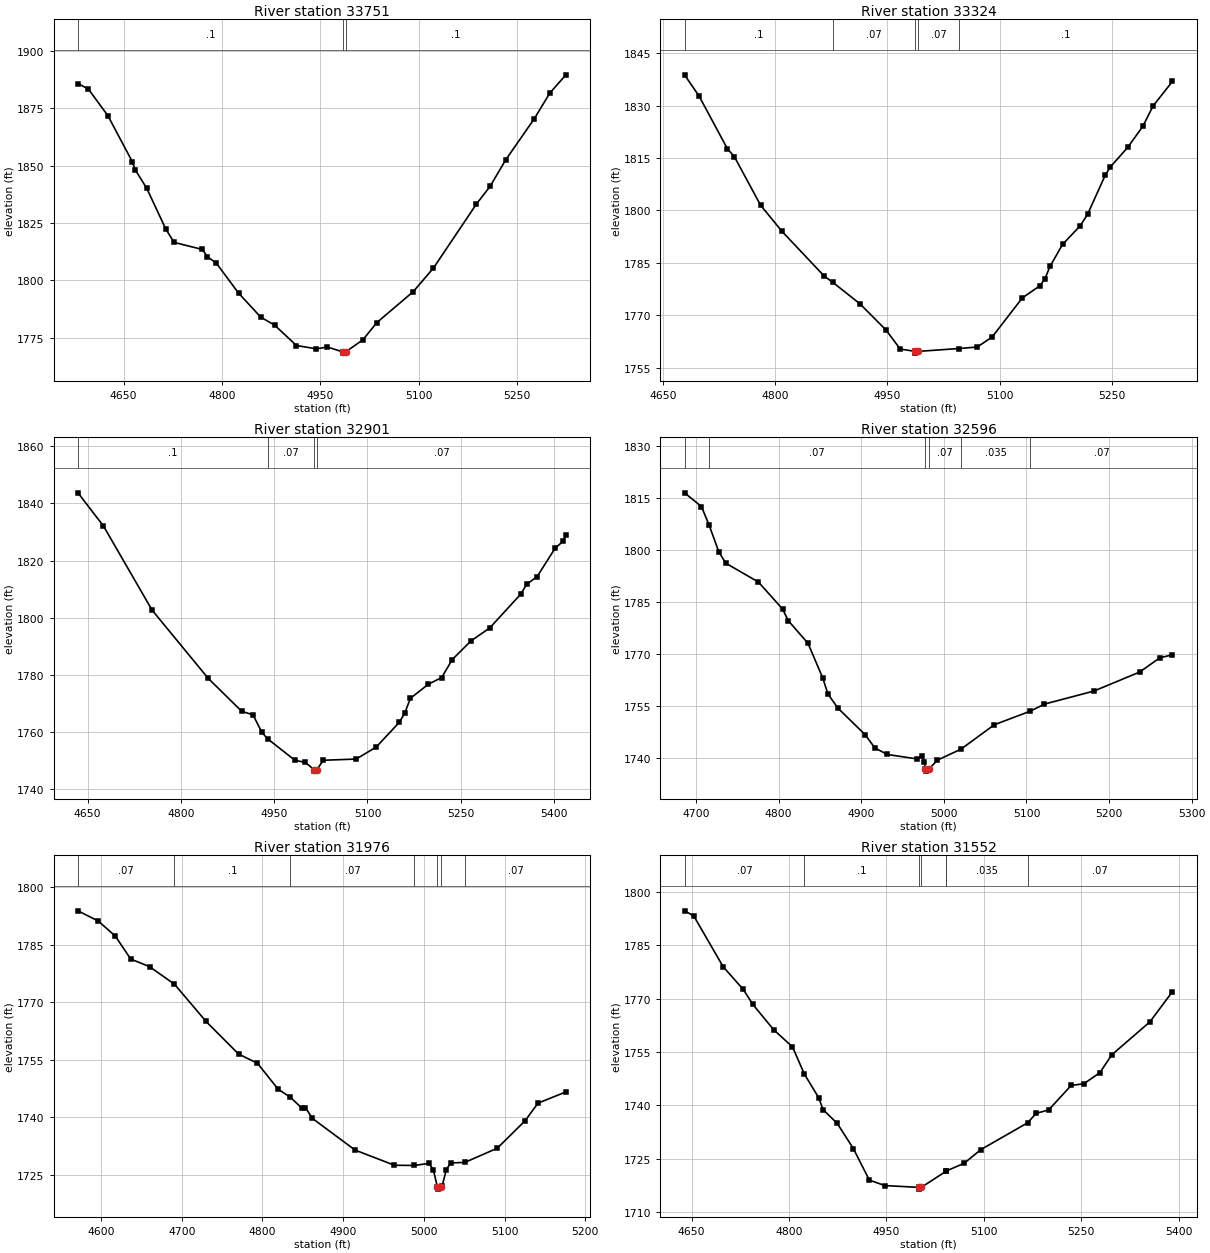
Type RM Length L Ch R = 1 ,33751   ,427,427,427
BEGIN DESCRIPTION:
Bruins Creek 71.0
END DESCRIPTION:
XS GIS Cut Line= 3
      1999725.03     13868824.97        2000025.       13868525.
      2000275.02     13868324.98
#Sta/Elev= 30
  4580.3  1885.8  4596.2 1883.39  4625.9 1871.81  4663.3 1851.66  4667.6 1848.19
  4685.3 1840.07  4714.2 1822.39    4727  1816.5  4770.1 1813.42  4777.9 1810.22
  4791.3 1807.49  4825.3 1794.39  4859.2 1783.88  4880.4  1780.4  4913.6 1771.52
  4944.1 1770.08    4961 1770.87  4984.5  1768.7  4984.7  1768.2  4988.5  1768.7
  5015.1 1774.03  5036.1 1781.48  5091.9 1795.05  5122.6 1805.29    5188 1833.16
    5209 1840.95    5233 1852.57  5276.2 1870.33  5300.2 1881.65  5324.7 1889.59
#Mann= 3 ,-1 , 0
  4580.3      .1       0  4984.5     .05       0  4988.5      .1       0
Bank Sta=4984.5,4988.5
XS Rating Curve= 0 ,0
Exp/Cntr=0.3,0.1

Type RM Length L Ch R = 1 ,33324   ,423,423,423
BEGIN DESCRIPTION:
Bruins Creek 70.0
END DESCRIPTION:
XS GIS Cut Line= 3
      1999924.98     13868975.01        2000225.       13868875.
      2000375.02     13868574.96
#Sta/Elev= 30
  4679.1 1838.79  4698.4 1832.76  4736.3 1817.66  4745.8 1815.31  4780.6  1801.5
    4809 1794.05    4866 1781.12  4877.1 1779.41  4913.4 1773.25  4948.2 1765.75
  4967.2  1760.3  4987.3 1759.64  4987.5 1759.14  4991.3 1759.64  5045.1 1760.45
    5070 1760.88    5090 1763.77  5130.3 1774.95  5153.8 1778.44  5160.5 1780.43
  5167.2 1783.95    5184 1790.25  5207.5 1795.57  5217.5 1798.92    5241 1810.07
  5247.7 1812.39  5271.2 1818.08  5291.3 1824.09  5304.8 1829.85  5330.8 1836.93
#Mann= 5 ,-1 , 0
  4679.1      .1       0  4877.1     .07       0  4987.3     .05       0
  4991.3     .07       0  5045.1      .1       0
Bank Sta=4987.3,4991.3
XS Rating Curve= 0 ,0
Exp/Cntr=0.3,0.1

Type RM Length L Ch R = 1 ,32901   ,305,305,305
BEGIN DESCRIPTION:
Bruins Creek 69.0
END DESCRIPTION:
XS GIS Cut Line= 3
      2000075.03     13869424.98        2000375.       13869225.
      2000675.01     13868924.99
#Sta/Elev= 30
  4634.4 1843.74  4675.4 1832.13  4753.6 1802.65  4843.8 1778.74  4897.9 1767.14
  4915.9 1765.95  4930.3 1759.77  4939.6  1757.5  4983.6 1749.96  4999.5 1749.32
  5014.5  1746.7  5014.7  1746.2  5018.5  1746.7  5029.2 1750.01  5081.9 1750.43
  5114.1 1754.63  5151.5 1763.36    5160 1766.56  5169.2 1771.75  5198.2 1776.69
  5219.4 1778.99  5236.4  1785.3  5266.8  1791.9  5296.5 1796.34  5346.7 1808.26
  5355.9 1811.64  5372.9 1814.38  5401.8  1824.3  5414.6 1826.76  5419.2 1828.86
#Mann= 4 ,-1 , 0
  4634.4      .1       0  4939.6     .07       0  5014.5     .05       0
  5018.5     .07       0
Bank Sta=5014.5,5018.5
XS Rating Curve= 0 ,0
Exp/Cntr=0.3,0.1

Type RM Length L Ch R = 1 ,32596   ,620,620,620
BEGIN DESCRIPTION:
Bruins Creek 68.0
END DESCRIPTION:
XS GIS Cut Line= 3
      2000162.72     13869498.54      2000464.39     13869499.95
      2000725.01       13869375.
#Sta/Elev= 30
  4686.1 1816.54  4706.6 1812.58  4715.8 1807.26  4727.6  1799.5  4736.1  1796.2
  4775.6 1790.75  4804.8 1782.96  4811.6 1779.63  4835.6 1773.05  4853.6 1762.93
  4859.6 1758.47  4871.6 1754.37  4904.6 1746.68  4916.6 1742.81  4931.6 1740.93
  4967.6 1739.65  4973.6 1740.52  4976.6 1738.73  4977.6 1736.62  4977.9 1736.12
  4981.6 1736.62  4992.1 1739.28  5020.7 1742.46  5061.1 1749.52  5104.7 1753.45
  5121.8 1755.49  5181.7 1759.26  5237.1 1764.75  5261.5 1768.88  5276.8 1769.73
#Mann= 6 ,-1 , 0
  4686.1      .1       0  4715.8     .07       0  4977.6     .05       0
  4981.6     .07       0  5020.7    .035       0  5104.7     .07       0
Bank Sta=4977.6,4981.6
XS Rating Curve= 0 ,0
Exp/Cntr=0.3,0.1

Type RM Length L Ch R = 1 ,31976   ,424,424,424
BEGIN DESCRIPTION:
Bruins Creek 67.0
END DESCRIPTION:
XS GIS Cut Line= 3
        2000125.       13869725.        2000425.       13870025.
      2000574.97     13870124.98
#Sta/Elev= 30
  4571.4 1793.83  4596.5 1791.18  4617.7 1787.24  4636.8 1781.26  4660.1 1779.28
    4691  1774.7  4730.1    1765  4770.5 1756.49  4793.8  1754.1  4819.2 1747.39
  4834.7  1745.2  4848.9  1742.4  4853.2 1742.57  4861.7 1739.75  4914.7 1731.48
  4963.5 1727.52  4987.9 1727.47  5006.1    1728  5011.6 1726.39  5016.8  1721.8
    5017  1721.3  5020.8  1721.8  5022.4 1721.99  5027.8 1726.41  5033.2 1728.12
  5050.8 1728.27  5090.9 1731.97  5125.1 1739.06  5141.4 1743.72  5175.9 1746.63
#Mann= 7 ,-1 , 0
  4571.4     .07       0    4691      .1       0  4834.7     .07       0
  4987.9    .035       0  5016.8    .035       0  5020.8    .035       0
  5050.8     .07       0
Bank Sta=5016.8,5020.8
XS Rating Curve= 0 ,0
Exp/Cntr=0.3,0.1

Type RM Length L Ch R = 1 ,31552   ,421,421,421
BEGIN DESCRIPTION:
Bruins Creek 66.0
END DESCRIPTION:
XS GIS Cut Line= 3
      1999924.98     13870174.99        2000225.       13870375.
      2000525.01     13870625.01
#Sta/Elev= 30
  4639.2  1794.7  4653.3  1793.3  4698.7 1778.97  4729.7 1772.57  4744.3 1768.39
  4776.5 1761.23  4805.4 1756.43  4823.6  1748.8  4845.8 1742.11  4852.4 1738.79
  4874.1 1734.94  4899.1 1727.81  4923.7 1718.95  4947.5 1717.41  4999.6 1716.91
  4999.8 1716.41  5003.6 1716.91  5041.4 1721.39  5042.3 1721.53  5069.7 1723.69
  5095.3 1727.53  5167.3 1735.06  5180.5 1737.74  5199.7 1738.69  5234.4 1745.59
  5253.9 1746.05  5278.5 1749.17  5296.9  1754.2  5355.5 1763.46  5390.3 1771.98
#Mann= 7 ,-1 , 0
  4639.2     .07       0  4823.6      .1       0  4999.6     .05       0
  5003.6      .1       0  5041.4     .07       0  5042.3    .035       0
  5167.3     .07       0
Bank Sta=4999.6,5003.6
XS Rating Curve= 0 ,0
Exp/Cntr=0.3,0.1

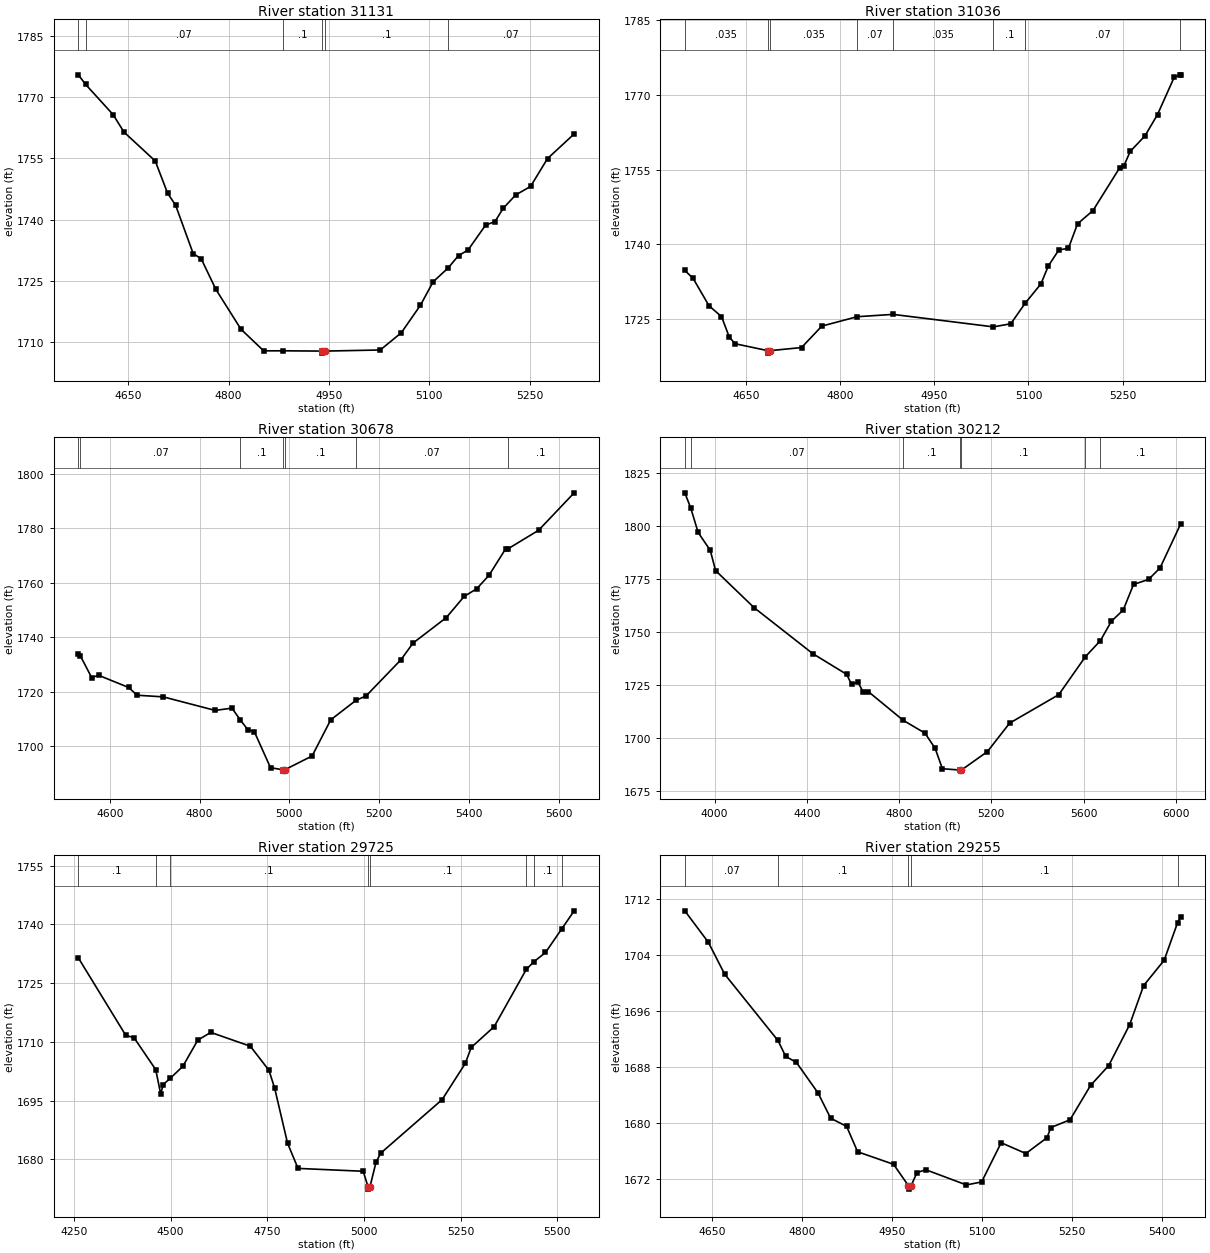
Type RM Length L Ch R = 1 ,31131   ,95,95,95
BEGIN DESCRIPTION:
Bruins Creek 65.0
END DESCRIPTION:
XS GIS Cut Line= 3
        1999825.       13870425.        2000125.       13870725.
      2000425.01       13870825.
#Sta/Elev= 30
  4575.7 1775.49  4586.5 1773.15  4627.7 1765.72  4643.9 1761.45  4690.6 1754.36
    4709 1746.47    4721 1743.52  4747.2 1731.68  4759.2  1730.4  4781.1  1722.9
  4818.6 1713.13  4852.5 1707.83  4881.3 1707.84  4939.6 1707.77  4939.9 1707.27
  4943.6 1707.77  5026.6 1708.04  5058.1 1712.27  5086.7 1719.03  5105.5 1724.74
  5127.8 1728.12  5143.6 1731.19  5157.7 1732.54  5183.8 1738.62    5198 1739.53
  5210.2 1742.76  5228.9 1746.05  5251.1 1748.13  5276.4 1754.96  5316.2    1761
#Mann= 6 ,-1 , 0
  4575.7      .1       0  4586.5     .07       0  4881.3      .1       0
  4939.6     .05       0  4943.6      .1       0  5127.8     .07       0
Bank Sta=4939.6,4943.6
XS Rating Curve= 0 ,0
Exp/Cntr=0.3,0.1

Type RM Length L Ch R = 1 ,31036   ,358,358,358
BEGIN DESCRIPTION:
Mapping XS 0dfbc96d
END DESCRIPTION:
XS GIS Cut Line= 6
      1999821.33     13870646.77      1999870.83     13870788.74
      2000064.84     13870834.31      2000171.61     13870805.67
      2000239.32     13870775.72      2000468.28     13870887.84
#Sta/Elev= 30
  4552.9 1734.79  4566.1 1733.19  4591.5 1727.68  4611.3 1725.52  4623.7 1721.42
  4632.8 1720.07  4684.9 1718.68  4685.1 1718.18  4688.9 1718.68  4738.7  1719.3
  4771.1 1723.61  4827.2 1725.49  4884.3 1725.96  5044.3 1723.45  5071.9 1724.08
  5094.5 1728.16  5119.8 1732.08  5131.7  1735.7  5148.4 1738.91  5163.5 1739.21
  5178.1 1744.14  5202.7 1746.81  5245.3 1755.42    5252 1755.83    5262 1758.68
  5285.4  1761.8  5305.4 1766.08  5332.1 1773.61  5341.6    1774  5342.2 1774.06
#Mann= 8 ,-1 , 0
  4552.9    .035       0  4684.9    .035       0  4688.9    .035       0
  4827.2     .07       0  4884.3    .035       0  5044.3      .1       0
  5094.5     .07       0  5341.6      .1       0
Bank Sta=4684.9,4688.9
XS Rating Curve= 0 ,0
Exp/Cntr=0.3,0.1

Type RM Length L Ch R = 1 ,30678   ,466,466,466
BEGIN DESCRIPTION:
Bruins Creek 64.0
END DESCRIPTION:
XS GIS Cut Line= 5
      1999790.73     13870648.78      1999891.54     13870991.54
        1999975.       13871075.      2000251.18      13871168.4
      2000581.73     13871097.14
#Sta/Elev= 30
  4529.8 1733.66  4534.4 1733.12  4559.5 1725.18  4575.1 1726.01  4641.8 1721.55
  4661.1  1718.7  4719.1  1718.1  4834.7 1713.13  4872.2 1713.96  4890.9 1709.61
  4907.2 1706.12    4922 1705.33  4958.1  1692.1  4985.8 1691.35    4986 1690.85
  4989.8 1691.35  5050.8 1696.41  5092.3 1709.67  5148.3  1716.8  5171.1 1718.46
  5248.5 1731.66  5275.6 1737.82  5349.9 1747.19  5389.8 1754.98  5417.4 1757.73
  5445.1 1762.72  5481.9 1772.37  5487.8 1772.47  5555.5 1779.22  5634.8 1792.97
#Mann= 7 ,-1 , 0
  4529.8    .035       0  4534.4     .07       0  4890.9      .1       0
  4985.8     .05       0  4989.8      .1       0  5148.3     .07       0
  5487.8      .1       0
Bank Sta=4985.8,4989.8
XS Rating Curve= 0 ,0
Exp/Cntr=0.3,0.1

Type RM Length L Ch R = 1 ,30212   ,487,487,487
BEGIN DESCRIPTION:
Bruins Creek 63.0
END DESCRIPTION:
XS GIS Cut Line= 3
      1998553.12     13871348.77        1999675.       13871425.
      2000665.55       13871161.
#Sta/Elev= 30
  3870.9 1815.72  3896.4 1808.64  3928.7    1797  3981.3 1788.53  4004.3 1778.98
  4170.9 1761.49  4425.3 1739.75  4572.6 1729.93  4593.7 1725.24  4621.4 1726.27
  4644.8 1721.41  4666.4 1721.78  4817.3 1708.25  4912.4 1702.12  4956.4 1694.91
  4987.6 1685.32    5066 1684.69  5066.3 1684.19  5070.1 1684.69  5182.9 1693.42
  5279.2 1706.88  5492.2 1720.33  5607.6 1738.26  5672.8 1745.86  5720.1    1755
  5771.6 1760.33  5816.3 1772.42  5881.5 1774.79  5931.2 1780.21  6020.5 1800.98
#Mann= 7 ,-1 , 0
  3870.9      .1       0  3896.4     .07       0  4817.3      .1       0
    5066     .05       0  5070.1      .1       0  5607.6     .07       0
  5672.8      .1       0
Bank Sta=5066,5070.1
XS Rating Curve= 0 ,0
Exp/Cntr=0.3,0.1

Type RM Length L Ch R = 1 ,29725   ,470,470,470
BEGIN DESCRIPTION:
Bruins Creek 62.0
END DESCRIPTION:
XS GIS Cut Line= 3
      1998938.78      13871929.6        1999675.       13871875.
      2000218.33     13871893.96
#Sta/Elev= 30
  4261.4 1731.44  4384.2 1711.63  4405.3 1711.07  4461.5  1702.9  4474.5 1696.62
  4480.3 1699.05  4499.2  1700.7  4531.6 1703.75  4570.2 1710.43  4603.8 1712.41
  4706.1 1708.88  4754.2 1702.73    4769 1698.16  4802.3 1684.12  4829.4 1677.68
  4997.9 1676.95  5010.7 1672.89    5011 1672.39  5015.1 1672.89  5030.9  1679.2
  5042.9 1681.55    5202 1695.25    5262 1704.52  5277.1 1708.56  5336.6 1713.89
  5419.6  1728.5  5439.1 1730.44  5469.2 1732.81  5510.8 1738.78  5543.3 1743.45
#Mann= 8 ,-1 , 0
  4261.4      .1       0  4461.5     .07       0  4499.2      .1       0
  5010.7     .05       0  5015.1      .1       0  5419.6     .07       0
  5439.1      .1       0  5510.8     .07       0
Bank Sta=5010.7,5015.1
XS Rating Curve= 0 ,0
Exp/Cntr=0.3,0.1

Type RM Length L Ch R = 1 ,29255   ,452,452,452
BEGIN DESCRIPTION:
Bruins Creek 61.0
END DESCRIPTION:
XS GIS Cut Line= 3
      1999174.98       13872225.        1999575.       13872225.
      1999974.98     13872374.99
#Sta/Elev= 30
  4604.7  1710.3    4644 1705.81  4671.2 1701.26  4760.1  1691.8    4773 1689.53
    4791 1688.66    4827 1684.31    4848 1680.71  4874.7 1679.54    4893 1675.92
    4953 1674.13  4977.7 1671.09    4978 1670.59  4982.3 1671.09    4992 1672.94
  5006.7 1673.36  5074.4 1671.19  5099.9 1671.61  5132.5 1677.21  5173.7 1675.67
    5209 1677.93  5215.4 1679.38  5247.4 1680.48  5281.6 1685.38  5311.9 1688.22
  5346.9 1694.06  5370.2 1699.64  5404.4 1703.24  5426.9 1708.63  5431.9 1709.43
#Mann= 5 ,-1 , 0
  4604.7     .07       0  4760.1      .1       0  4977.7     .05       0
  4982.3      .1       0  5426.9     .07       0
Bank Sta=4977.7,4982.3
XS Rating Curve= 0 ,0
Exp/Cntr=0.3,0.1

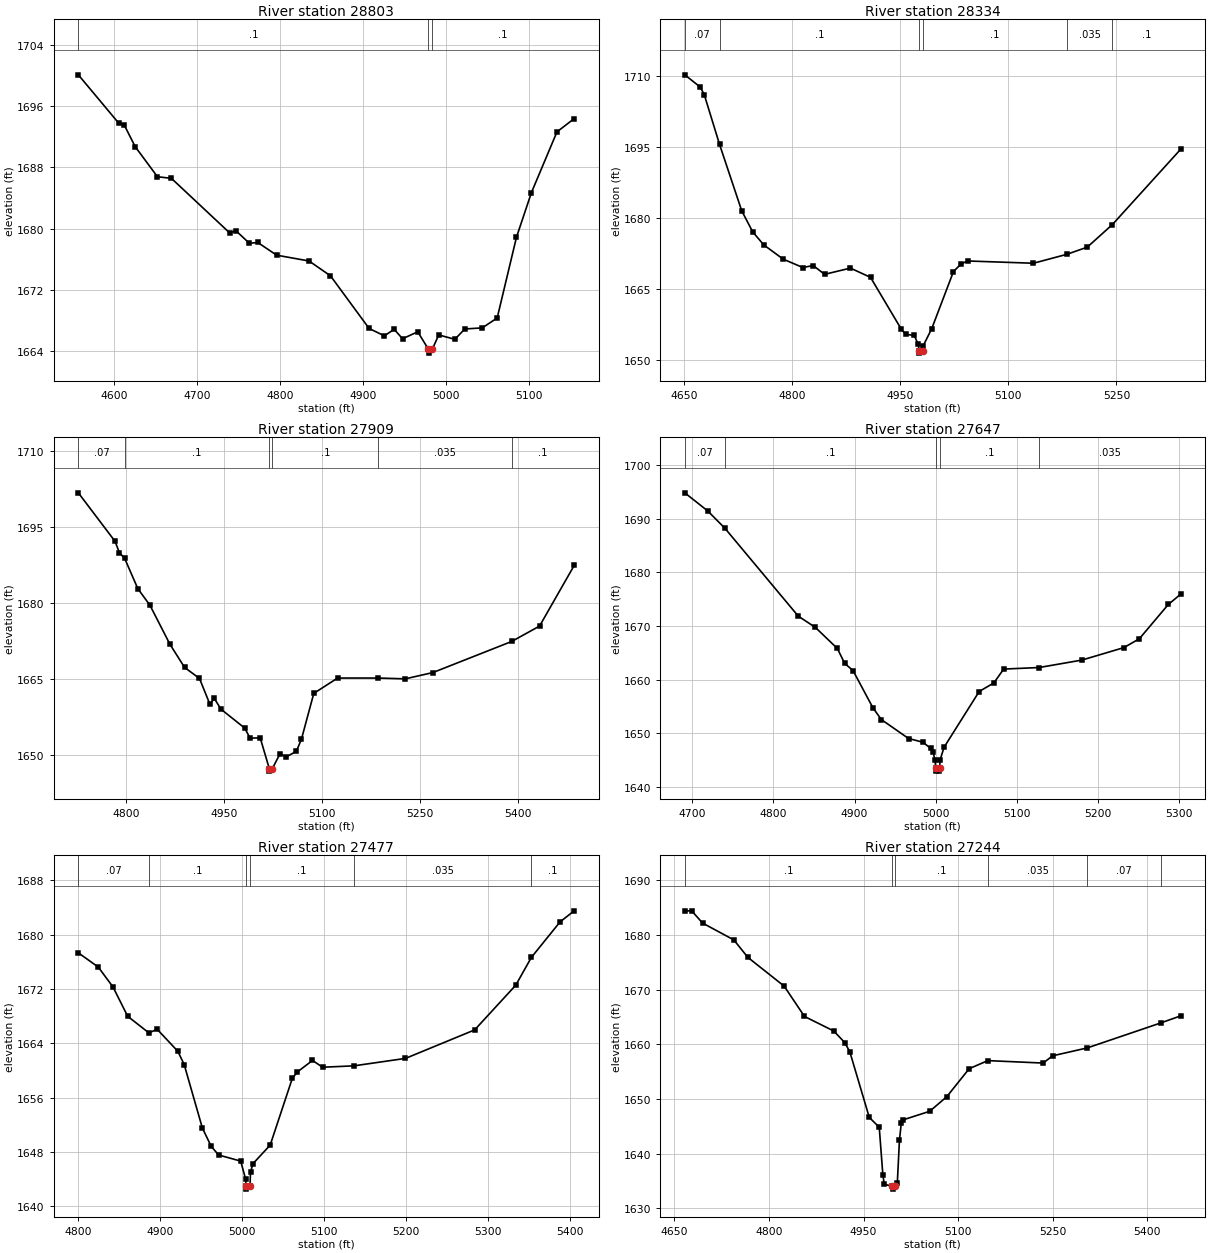
Type RM Length L Ch R = 1 ,28803   ,469,469,469
BEGIN DESCRIPTION:
Bruins Creek 60.0
END DESCRIPTION:
XS GIS Cut Line= 3
        1999225.       13872425.        1999625.       13872625.
      1999774.99       13872625.
#Sta/Elev= 30
  4557.1 1700.12  4605.5 1693.83  4612.2  1693.6  4625.6 1690.72  4652.4 1686.79
  4669.2 1686.58  4739.6 1679.42  4746.8 1679.74  4763.1 1678.09  4773.2 1678.19
    4796 1676.53    4835 1675.77  4860.8 1673.83  4907.3 1666.95  4925.7 1665.98
  4937.5 1666.84  4947.6  1665.6  4965.9 1666.51  4978.8 1664.22  4979.1 1663.72
  4983.4 1664.22  4991.2  1666.1  5010.6 1665.53  5022.6 1666.88  5043.6 1667.02
  5061.6 1668.32  5084.8 1678.87  5102.8 1684.71  5133.6 1692.66  5154.3 1694.39
#Mann= 3 ,-1 , 0
  4557.1      .1       0  4978.8     .05       0  4983.4      .1       0
Bank Sta=4978.8,4983.4
XS Rating Curve= 0 ,0
Exp/Cntr=0.3,0.1

Type RM Length L Ch R = 1 ,28334   ,425,425,425
BEGIN DESCRIPTION:
Bruins Creek 59.0
END DESCRIPTION:
XS GIS Cut Line= 3
      1999175.01       13872975.        1999525.       13873025.
      1999859.45     13873022.59
#Sta/Elev= 30
  4651.1 1710.34  4672.6 1707.74  4678.1 1706.14  4699.3 1695.61  4730.1 1681.53
  4745.3 1677.08  4760.7 1674.31  4787.7 1671.29    4815 1669.52  4829.2 1669.95
  4845.1 1668.08  4880.9  1669.4  4908.8 1667.44  4951.6 1656.44  4957.4 1655.38
  4969.5 1655.14    4975 1653.25  4976.3 1651.89  4976.6 1651.39    4981 1651.89
  4981.7 1652.88  4993.8 1656.59  5023.9 1668.67  5034.4 1670.27  5043.4 1670.91
  5134.9 1670.43    5181 1672.31  5209.6 1673.84  5244.4 1678.62  5339.1 1694.56
#Mann= 6 ,-1 , 0
  4651.1     .07       0  4699.3      .1       0  4976.3     .05       0
    4981      .1       0    5181    .035       0  5244.4      .1       0
Bank Sta=4976.3,4981
XS Rating Curve= 0 ,0
Exp/Cntr=0.3,0.1

Type RM Length L Ch R = 1 ,27909   ,262,262,262
BEGIN DESCRIPTION:
Bruins Creek 58.0
END DESCRIPTION:
XS GIS Cut Line= 3
      1999074.96     13873274.98        1999325.       13873375.
       1999808.8     13873455.75
#Sta/Elev= 30
  4726.7 1701.79    4783 1692.21  4789.5 1690.01  4797.7 1688.85  4817.9 1682.87
  4836.4 1679.61    4867 1671.92  4889.5 1667.33  4912.3 1665.17  4928.4 1660.04
  4934.9 1661.23  4945.5 1659.07  4981.8 1655.35  4989.8 1653.38  5005.4 1653.44
  5019.3 1647.37  5019.6 1646.87    5024 1647.37  5035.8  1650.3  5045.1 1649.68
  5060.7 1650.76  5068.6 1653.17  5087.5 1662.21    5124 1665.24  5186.5 1665.24
  5227.6 1665.08    5270 1666.32    5391 1672.47  5433.5  1675.5  5486.5 1687.45
#Mann= 6 ,-1 , 0
  4726.7     .07       0  4797.7      .1       0  5019.3     .05       0
    5024      .1       0  5186.5    .035       0    5391      .1       0
Bank Sta=5019.3,5024
XS Rating Curve= 0 ,0
Exp/Cntr=0.3,0.1

Type RM Length L Ch R = 1 ,27647   ,170,170,170
BEGIN DESCRIPTION:
Mapping XS a820c766
END DESCRIPTION:
XS GIS Cut Line= 2
      1998964.09     13873589.08      1999572.36     13873650.86
#Sta/Elev= 30
  4690.7  1694.8    4719 1691.42  4740.2 1688.19  4830.6 1671.82  4851.6 1669.73
  4878.8 1665.79  4887.9    1663  4898.1 1661.68  4922.8  1654.7  4933.1 1652.54
  4966.6 1649.01  4984.4 1648.32    4994 1647.15  4996.7 1646.49  4999.3 1645.03
  5000.1 1643.43  5000.4 1642.93  5004.5 1642.93  5004.9 1643.43  5005.5 1645.02
  5010.4 1647.38  5053.7 1657.77  5071.8 1659.37  5083.9 1661.95  5127.6 1662.24
  5180.4 1663.63  5232.1 1665.95  5251.2  1667.6  5286.9 1673.99  5302.1  1675.9
#Mann= 5 ,-1 , 0
  4690.7     .07       0  4740.2      .1       0  5000.1     .05       0
  5004.9      .1       0  5127.6    .035       0
Bank Sta=5000.1,5004.9
XS Rating Curve= 0 ,0
Exp/Cntr=0.3,0.1

Type RM Length L Ch R = 1 ,27477   ,233,233,233
BEGIN DESCRIPTION:
Bruins Creek 57.0
END DESCRIPTION:
XS GIS Cut Line= 3
        1999025.       13873775.        1999225.       13873775.
      1999630.49     13873784.31
#Sta/Elev= 30
    4800 1677.34  4824.3 1675.25  4842.3 1672.32  4860.3 1667.99  4886.2 1665.55
  4896.3 1666.08  4921.5 1662.84  4929.3 1660.88  4951.5 1651.53  4962.3 1648.83
  4971.3 1647.56  4998.3 1646.66  5004.3 1644.01  5004.9 1643.03  5005.2 1642.53
  5009.7 1643.03  5010.3 1645.03  5013.3 1646.28  5034.3 1649.01  5061.3 1658.83
  5067.3 1659.77    5086 1661.49  5098.3 1660.49  5136.5 1660.69  5199.6 1661.79
  5284.1 1665.99  5334.3 1672.58  5353.4 1676.68  5388.4  1681.9  5405.6 1683.53
#Mann= 6 ,-1 , 0
    4800     .07       0  4886.2      .1       0  5004.9     .05       0
  5009.7      .1       0  5136.5    .035       0  5353.4      .1       0
Bank Sta=5004.9,5009.7
XS Rating Curve= 0 ,0
Exp/Cntr=0.3,0.1

Type RM Length L Ch R = 1 ,27244   ,217,217,217
BEGIN DESCRIPTION:
Mapping XS 3bbc0589
END DESCRIPTION:
XS GIS Cut Line= 3
      1998881.68     13873805.42      1999165.08     13873992.21
      1999612.35     13873990.83
#Sta/Elev= 30
  4666.4 1684.45  4677.5 1684.43  4694.6 1682.21  4744.2 1679.13  4766.5 1675.93
    4824 1670.68  4856.3 1665.13  4902.8 1662.46  4920.1 1660.36  4928.2 1658.67
  4959.1 1646.66  4974.9 1644.86  4980.7 1636.07  4982.9 1634.45  4995.6 1634.04
    4996 1633.54  5000.4 1634.04  5003.6 1634.71    5007 1642.54    5010 1645.72
    5013 1646.22    5055 1647.78    5082 1650.44  5117.6 1655.57  5147.2 1657.05
    5235  1656.6    5250 1657.93  5304.9 1659.37  5421.3 1663.93  5453.1 1665.23
#Mann= 6 ,-1 , 0
  4666.4      .1       0  4995.6     .05       0  5000.4      .1       0
  5147.2    .035       0  5304.9     .07       0  5421.3    .035       0
Bank Sta=4995.6,5000.4
XS Rating Curve= 0 ,0
Exp/Cntr=0.3,0.1

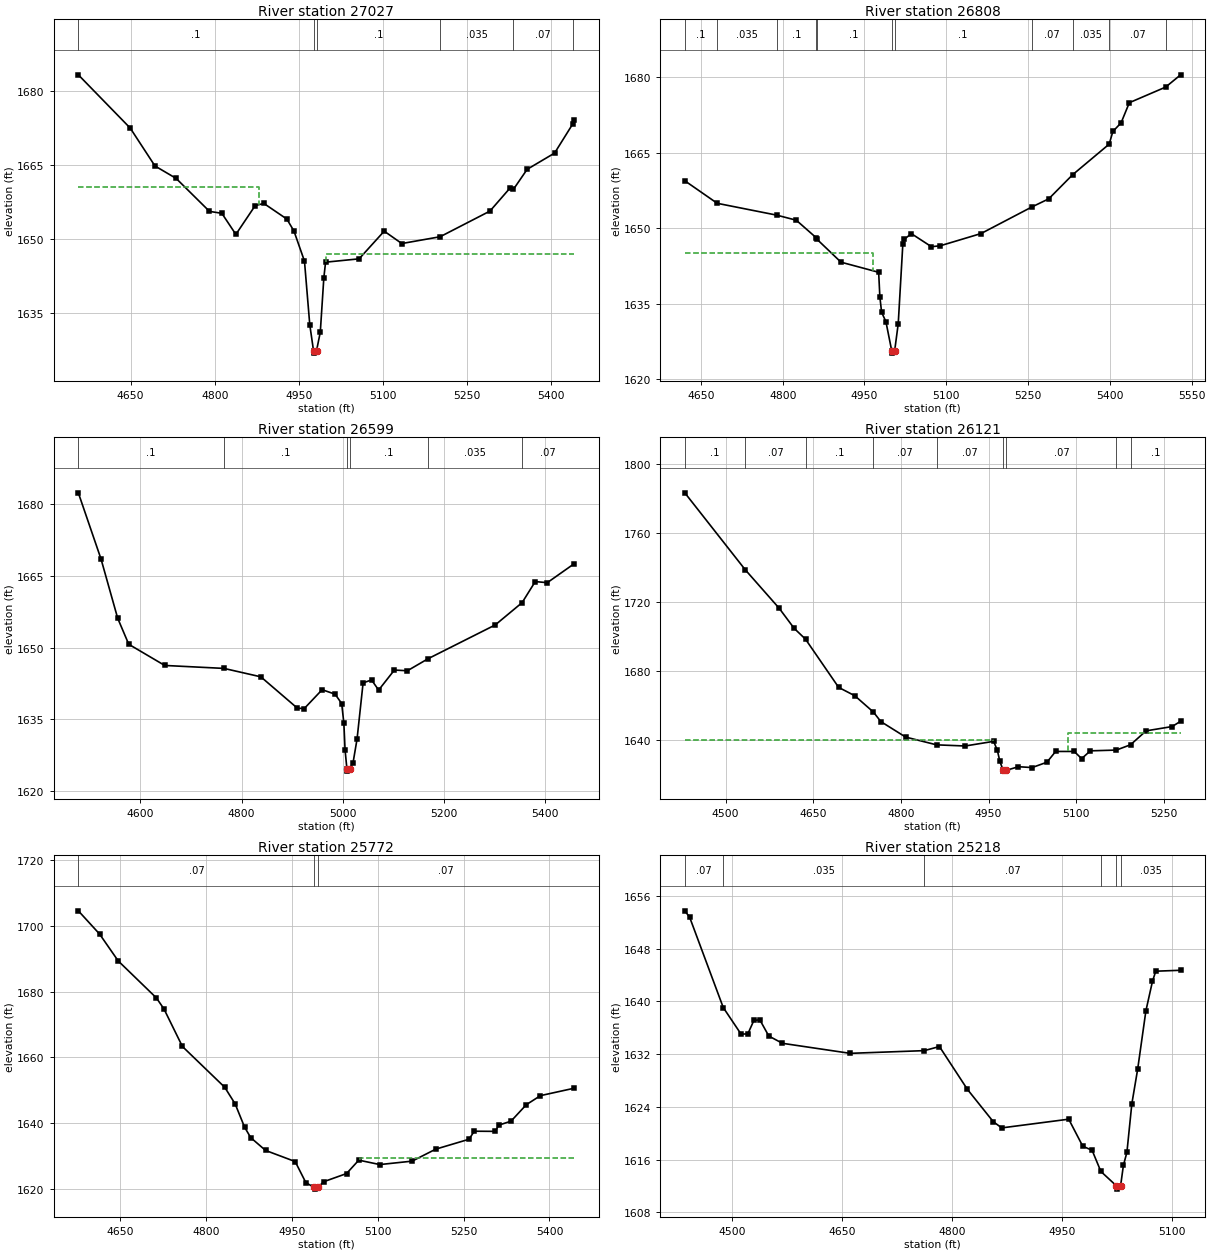
Type RM Length L Ch R = 1 ,27027   ,219,219,219
BEGIN DESCRIPTION:
Bruins Creek 56.0
END DESCRIPTION:
XS GIS Cut Line= 3
      1998651.48     13874046.71        1999075.       13874175.
      1999454.22     13874400.64
#Sta/Elev= 30
  4556.8 1683.22  4649.3 1672.42  4693.4 1664.74  4731.1 1662.22  4790.6 1655.53
  4812.6 1655.14  4837.6 1650.86  4872.1 1656.71  4887.5 1657.14  4928.4 1653.98
  4941.1 1651.56  4959.9 1645.44  4969.3 1632.59    4976 1627.29  4976.4 1626.79
  4981.4 1627.29  4988.1 1631.05  4994.4 1642.06  4997.5 1645.23  5057.3 1645.91
    5102 1651.52  5133.4 1649.01  5201.7 1650.39  5290.5 1655.59  5326.5 1660.29
  5332.3 1659.99  5356.8 1664.06  5405.7 1667.35  5438.2 1673.28  5440.6 1674.14
#Mann= 6 ,-1 , 0
  4556.8      .1       0    4976     .05       0  4981.4      .1       0
  5201.7    .035       0  5332.3     .07       0  5438.2      .1       0
#XS Ineff= 2 , 0
         4878.92 1660.42 4998.65         1646.82
Permanent Ineff=
       F       F
Bank Sta=4976,4981.4
XS Rating Curve= 0 ,0
Exp/Cntr=0.3,0.1

Type RM Length L Ch R = 1 ,26808   ,209,209,209
BEGIN DESCRIPTION:
Mapping XS be7c4774
END DESCRIPTION:
XS GIS Cut Line= 3
      1998705.63     13874182.75      1999158.69     13874420.62
      1999553.71     13874467.53
#Sta/Elev= 30
  4620.4 1659.41  4679.9 1654.93  4789.4 1652.57  4824.9 1651.57  4861.2 1648.11
  4862.4 1647.83  4906.9 1643.23    4976 1641.22  4978.2 1636.34  4981.4 1633.27
  4989.3 1631.41  4999.9 1625.65  5000.4 1625.15  5005.4 1625.65  5011.9    1631
  5020.4 1646.94  5022.6 1647.75    5036  1648.9  5072.9  1646.3  5089.3  1646.5
  5163.8 1648.92  5256.6 1654.18    5288 1655.82  5331.7  1660.6  5398.9  1666.7
  5405.6 1669.21  5420.7 1670.93  5435.8 1674.93  5502.4 1678.03  5529.9 1680.47
#Mann= 11 ,-1 , 0
  4620.4      .1       0  4679.9    .035       0  4789.4      .1       0
  4861.2    .035       0  4862.4      .1       0  4999.9     .05       0
  5005.4      .1       0  5256.6     .07       0  5331.7    .035       0
  5398.9     .07       0  5502.4      .1       0
#XS Ineff= 2 , 0
         4965.47 1644.99
Permanent Ineff=
       F       F
Bank Sta=4999.9,5005.4
XS Rating Curve= 0 ,0
Exp/Cntr=0.3,0.1

Type RM Length L Ch R = 1 ,26599   ,478,478,478
BEGIN DESCRIPTION:
Bruins Creek 55.0
END DESCRIPTION:
XS GIS Cut Line= 3
      1998522.51     13874191.72        1998925.       13874525.
      1999359.36     13874667.18
#Sta/Elev= 30
  4477.4 1682.39  4522.3 1668.52  4555.1 1656.18    4577 1650.72  4648.1 1646.29
  4765.2 1645.67    4838 1643.91  4910.1 1637.36  4923.7 1637.27  4959.1 1641.22
  4984.7 1640.28  4997.7 1638.33    5002 1634.21  5004.4  1628.6    5008 1624.69
  5008.4 1624.19  5013.6 1624.69  5020.2 1625.97  5028.1 1630.92    5040 1642.64
  5056.7 1643.26  5070.7 1641.14  5101.8 1645.33  5127.5 1645.18  5168.6 1647.71
  5301.2 1654.77  5354.2 1659.43  5380.1 1663.83  5403.9  1663.6    5457 1667.56
#Mann= 6 ,-1 , 0
  4477.4      .1       0  4765.2      .1       0    5008     .05       0
  5013.6      .1       0  5168.6    .035       0  5354.2     .07       0
Bank Sta=5008,5013.6
XS Rating Curve= 0 ,0
Exp/Cntr=0.3,0.1

Type RM Length L Ch R = 1 ,26121   ,349,349,349
BEGIN DESCRIPTION:
Bruins Creek 54.0
END DESCRIPTION:
XS GIS Cut Line= 3
      1998125.03     13874325.03        1998525.       13874725.
      1998725.01     13874925.01
#Sta/Elev= 30
  4430.1 1783.52  4533.5 1738.78  4591.6 1716.37  4617.1 1704.74  4636.7 1698.37
  4693.4 1670.33    4721 1665.48  4752.9 1655.97  4765.6 1650.44    4808 1641.43
    4861 1636.91  4909.8 1636.24  4958.6 1638.94    4965 1633.66  4969.2 1627.35
  4974.9 1622.12  4975.4 1621.62  4980.6 1622.12    5001 1624.19  5024.4 1623.69
  5049.8  1626.8  5064.7 1633.06  5096.5 1633.07  5109.2 1628.88  5124.1 1633.42
  5168.6 1633.87  5192.9 1636.96  5219.5 1645.05  5264.1 1647.55  5278.6 1650.65
#Mann= 9 ,-1 , 0
  4430.1      .1       0  4533.5     .07       0  4636.7      .1       0
  4752.9     .07       0    4861     .07       0  4974.9     .05       0
  4980.6     .07       0  5168.6     .07       0  5192.9      .1       0
#XS Ineff= 2 , 0
         4958.29 1639.79  5086.1         1643.62
Permanent Ineff=
       F       F
#Block Obstruct= 2 , 0
                         5095.39         1633.09
Bank Sta=4974.9,4980.6
XS Rating Curve= 0 ,0
Exp/Cntr=0.3,0.1

Type RM Length L Ch R = 1 ,25772   ,554,554,554
BEGIN DESCRIPTION:
Bruins Creek 53.0
END DESCRIPTION:
XS GIS Cut Line= 3
      1998024.96     13874774.98      1998373.09     13875012.78
      1998809.55     13875098.03
#Sta/Elev= 30
  4576.8 1704.49  4613.8 1697.47  4646.5 1689.29  4713.2 1678.07  4726.4 1674.73
  4758.6 1663.35  4832.6 1650.96  4850.8 1645.92  4867.2 1638.89    4878 1635.69
  4903.9 1631.81  4955.7 1628.43  4974.4 1622.01  4989.3 1620.57  4989.8 1620.07
    4995 1620.57  5005.7 1622.33  5045.4 1624.79  5066.8 1628.86  5103.5 1627.52
    5160 1628.56  5201.3  1632.2  5259.4  1635.2  5268.6 1637.64  5305.2 1637.59
  5311.4 1639.48  5332.8 1640.69  5359.5 1645.68  5384.2 1648.43  5443.1 1650.68
#Mann= 3 ,-1 , 0
  4576.8     .07       0  4989.3     .05       0    4995     .07       0
#XS Ineff= 2 , 0
                         5068.61         1629.45
Permanent Ineff=
       F       F
Bank Sta=4989.3,4995
XS Rating Curve= 0 ,0
Exp/Cntr=0.3,0.1

Type RM Length L Ch R = 1 ,25218   ,470,470,470
BEGIN DESCRIPTION:
Bruins Creek 52.0
END DESCRIPTION:
XS GIS Cut Line= 3
      1998043.45     13875059.75        1998425.       13875475.
      1998524.98     13875524.99
#Sta/Elev= 30
  4435.8 1653.71  4442.4 1652.74  4488.2 1639.05  4512.5 1635.02  4521.7 1635.06
  4529.9 1637.09    4538  1637.2  4550.3 1634.73  4568.9 1633.63  4661.1 1632.11
  4762.1 1632.52  4782.8 1633.14    4821 1626.64  4856.1 1621.76  4867.7 1620.81
    4959 1622.13  4978.1 1618.04  4990.9 1617.41  5002.8 1614.21    5024 1612.03
  5024.4 1611.53  5029.7 1612.03  5033.5 1615.12  5038.3 1617.11    5045 1624.45
    5053 1629.74  5064.2 1638.57  5073.1 1643.01  5077.6 1644.56  5111.5  1644.7
#Mann= 6 ,-1 , 0
  4435.8     .07       0  4488.2    .035       0  4762.1     .07       0
  5002.8    .035       0    5024     .05       0  5029.7    .035       0
Bank Sta=5024,5029.7
XS Rating Curve= 0 ,0
Exp/Cntr=0.3,0.1