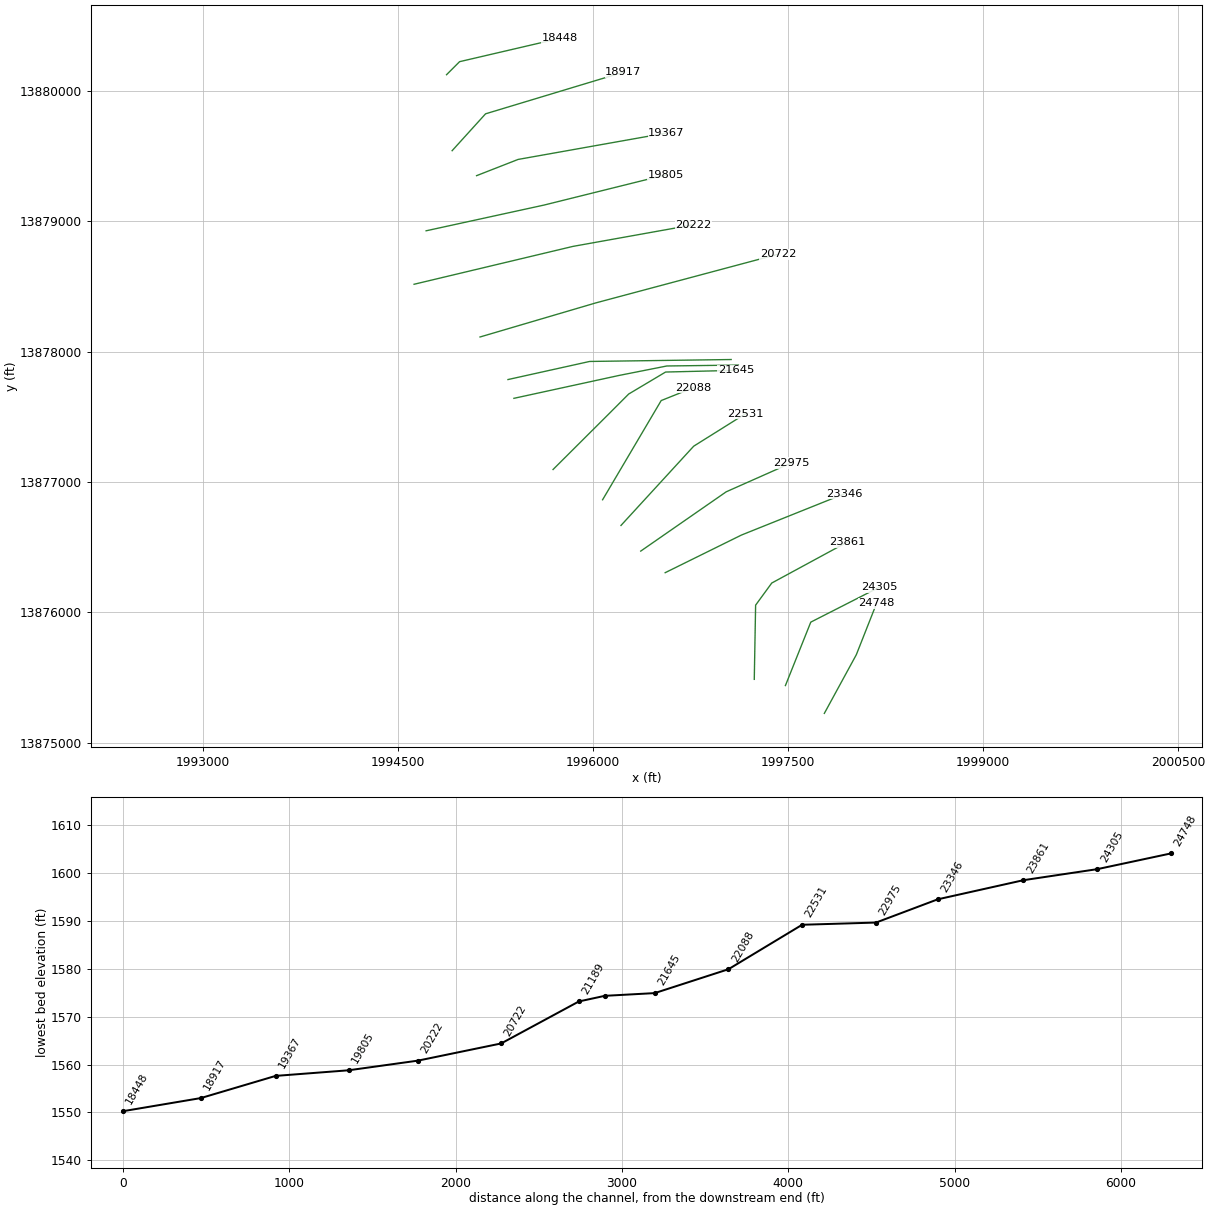
HEC-RAS study Bruins Creek.prj: Bruins Creek Base Level Engineering

--- Bruins Creek.g01 (geometry) --- (continued)

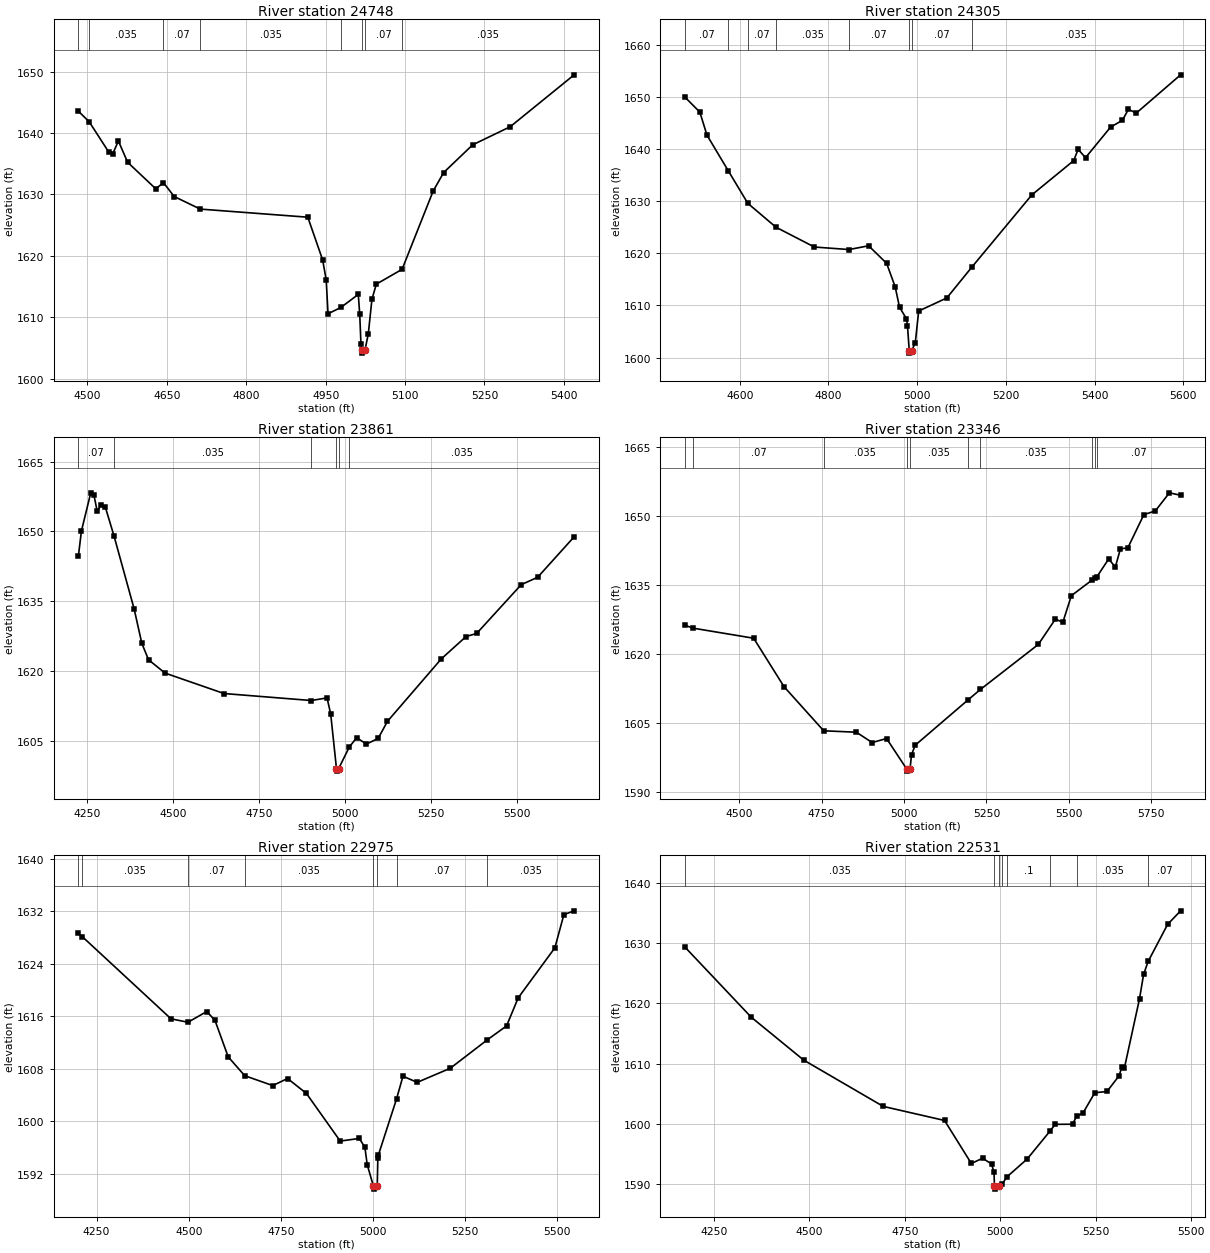
Type RM Length L Ch R = 1 ,24748   ,443,443,443
BEGIN DESCRIPTION:
Bruins Creek 51.0
END DESCRIPTION:
XS GIS Cut Line= 3
      1997779.19     13875224.96        1998025.       13875675.
      1998180.93      13876069.4
#Sta/Elev= 30
  4482.7 1643.55  4503.3 1641.81  4540.5 1636.84  4547.7  1636.6  4558.4 1638.69
  4575.8 1635.23  4628.9 1630.91  4643.6 1631.89    4664 1629.64  4713.1  1627.6
  4916.3 1626.28  4944.3 1619.34  4951.1 1616.07  4954.5 1610.56  4978.7 1611.58
  5011.7 1613.71  5014.4 1610.51  5016.7  1605.7  5018.4 1604.65  5018.9 1604.15
  5024.3 1604.65  5030.6 1607.27  5037.5 1612.92  5045.8 1615.38  5094.5  1617.8
  5153.1 1630.52    5173 1633.55  5227.8 1638.06  5298.8 1641.01  5419.6 1649.46
#Mann= 8 ,-1 , 0
  4482.7     .07       0  4503.3    .035       0  4643.6     .07       0
  4713.1    .035       0  4978.7     .07       0  5018.4     .05       0
  5024.3     .07       0  5094.5    .035       0
Bank Sta=5018.4,5024.3
XS Rating Curve= 0 ,0
Exp/Cntr=0.3,0.1

Type RM Length L Ch R = 1 ,24305   ,444,444,444
BEGIN DESCRIPTION:
Bruins Creek 50.0
END DESCRIPTION:
XS GIS Cut Line= 3
        1997480.      13875438.5        1997675.       13875925.
      1998204.63     13876194.33
#Sta/Elev= 30
  4475.9 1649.94  4509.8 1647.05  4525.9 1642.63  4574.1 1635.78  4618.1 1629.56
  4681.5 1624.99  4768.2 1621.19  4846.3 1620.71  4890.5 1621.43  4931.1 1618.07
  4950.4 1613.56  4960.2 1609.66  4975.8 1607.44  4978.1 1606.14  4982.1 1601.36
  4982.6 1600.86    4988 1601.36  4995.8 1602.89  5003.4 1608.93  5066.8 1611.43
  5123.6 1617.37  5258.6 1631.18  5352.9 1637.74    5363  1639.9  5379.8 1638.32
  5436.2 1644.17    5463 1645.48  5476.4 1647.58  5494.2 1646.86  5594.2 1654.19
#Mann= 8 ,-1 , 0
  4475.9     .07       0  4574.1    .035       0  4618.1     .07       0
  4681.5    .035       0  4846.3     .07       0  4982.1     .05       0
    4988     .07       0  5123.6    .035       0
Bank Sta=4982.1,4988
XS Rating Curve= 0 ,0
Exp/Cntr=0.3,0.1

Type RM Length L Ch R = 1 ,23861   ,515,515,515
BEGIN DESCRIPTION:
Bruins Creek 49.0
END DESCRIPTION:
XS GIS Cut Line= 4
      1997240.56     13875485.99      1997250.88      13876055.3
        1997375.       13876225.      1997956.81     13876539.88
#Sta/Elev= 30
  4225.2 1644.63  4234.2 1650.11  4261.3  1658.3  4270.3 1657.88  4280.2  1654.3
  4291.3 1655.75  4303.3 1655.32  4328.6 1649.13  4387.3  1633.4  4409.7    1626
  4429.3 1622.45  4477.3  1619.6  4648.6 1615.21  4902.2 1613.71  4948.1 1614.27
  4958.7 1610.83  4975.6 1599.05  4976.1 1598.55  4981.6 1599.05  5012.7 1603.71
  5034.3 1605.74  5062.3 1604.35  5096.7 1605.57  5123.7 1609.24  5280.4 1622.66
  5352.2 1627.45  5382.9  1628.1  5512.5 1638.58  5560.3 1640.17  5666.4 1648.86
#Mann= 6 ,-1 , 0
  4225.2     .07       0  4328.6    .035       0  4902.2     .07       0
  4975.6     .05       0  4981.6     .07       0  5012.7    .035       0
Bank Sta=4975.6,4981.6
XS Rating Curve= 0 ,0
Exp/Cntr=0.3,0.1

Type RM Length L Ch R = 1 ,23346   ,371,371,371
BEGIN DESCRIPTION:
Bruins Creek 48.0
END DESCRIPTION:
XS GIS Cut Line= 3
      1996555.66     13876304.38        1997142.     13876593.16
      1997931.07     13876908.91
#Sta/Elev= 30
  4335.3 1626.32  4360.5 1625.67  4544.1 1623.48  4636.1 1612.94  4756.5 1603.33
  4855.5 1603.02  4903.6 1600.77  4947.1 1601.65  5007.8 1595.05  5008.3 1594.55
  5018.3 1595.05  5022.8  1598.1  5033.8 1600.18  5194.4 1610.07  5231.9 1612.34
  5407.3 1622.13    5459 1627.64  5481.7 1626.95  5507.5 1632.75  5570.8 1636.17
  5580.2 1636.49  5583.8 1636.74  5620.6 1640.73  5640.8 1638.97  5656.2 1642.93
  5678.8 1643.16  5727.2 1650.37  5762.1  1651.2  5804.8 1655.13  5838.8  1654.6
#Mann= 10 ,-1 , 0
  4335.3    .035       0  4360.5     .07       0  4756.5    .035       0
  5007.8    .035       0  5018.3    .035       0  5194.4     .07       0
  5231.9    .035       0  5570.8     .07       0  5580.2    .035       0
  5583.8     .07       0
Bank Sta=5007.8,5018.3
XS Rating Curve= 0 ,0
Exp/Cntr=0.3,0.1

Type RM Length L Ch R = 1 ,22975   ,444,444,444
BEGIN DESCRIPTION:
Bruins Creek 47.0
END DESCRIPTION:
XS GIS Cut Line= 3
      1996367.68     13876469.95        1997025.       13876925.
      1997524.31     13877146.25
#Sta/Elev= 30
  4200.5 1628.69    4211 1628.16    4452 1615.63  4498.1 1615.11    4549 1616.74
  4571.2 1615.41  4607.2 1609.84    4652 1606.97  4728.1 1605.46  4768.3 1606.54
  4819.4 1604.27  4911.2 1597.01    4963 1597.41  4978.1 1596.08  4984.5 1593.41
  5001.1 1590.19  5001.6 1589.69  5011.7 1590.19  5013.3 1594.36  5014.7 1594.87
  5064.1 1603.43  5081.5 1606.89  5120.1 1605.95  5209.9  1608.1  5310.4 1612.43
  5362.6 1614.55  5394.4 1618.84  5493.7 1626.44  5518.2  1631.5  5546.1 1632.08
#Mann= 8 ,-1 , 0
  4200.5     .07       0    4211    .035       0  4498.1     .07       0
    4652    .035       0  5001.1    .035       0  5011.7    .035       0
  5064.1     .07       0  5310.4    .035       0
Bank Sta=5001.1,5011.7
XS Rating Curve= 0 ,0
Exp/Cntr=0.3,0.1

Type RM Length L Ch R = 1 ,22531   ,443,443,443
BEGIN DESCRIPTION:
Bruins Creek 46.0
END DESCRIPTION:
XS GIS Cut Line= 3
      1996215.88     13876666.83        1996775.       13877275.
      1997174.98     13877524.99
#Sta/Elev= 30
  4174.1 1629.34  4347.9 1617.71  4485.3  1610.6  4693.5 1602.93    4854  1600.6
  4924.1 1593.48  4953.8 1594.35  4977.1 1593.38  4983.5 1591.99  4984.6 1589.73
  4985.1 1589.23  4995.2 1589.73  5004.7 1590.05  5016.9 1591.24  5070.3 1594.22
  5130.9 1598.91  5143.6 1599.96  5188.9 1599.98  5200.1 1601.34    5216 1601.79
  5247.2 1605.19  5279.2  1605.4  5310.8    1608  5317.9 1609.43  5324.9 1609.34
  5364.3 1620.76    5375 1624.79  5386.8 1626.93  5437.9 1633.08  5471.9 1635.32
#Mann= 8 ,-1 , 0
  4174.1    .035       0  4984.6    .035       0  4995.2    .035       0
  5004.7     .07       0  5016.9      .1       0  5130.9     .07       0
  5200.1    .035       0  5386.8     .07       0
Bank Sta=4984.6,4995.2
XS Rating Curve= 0 ,0
Exp/Cntr=0.3,0.1

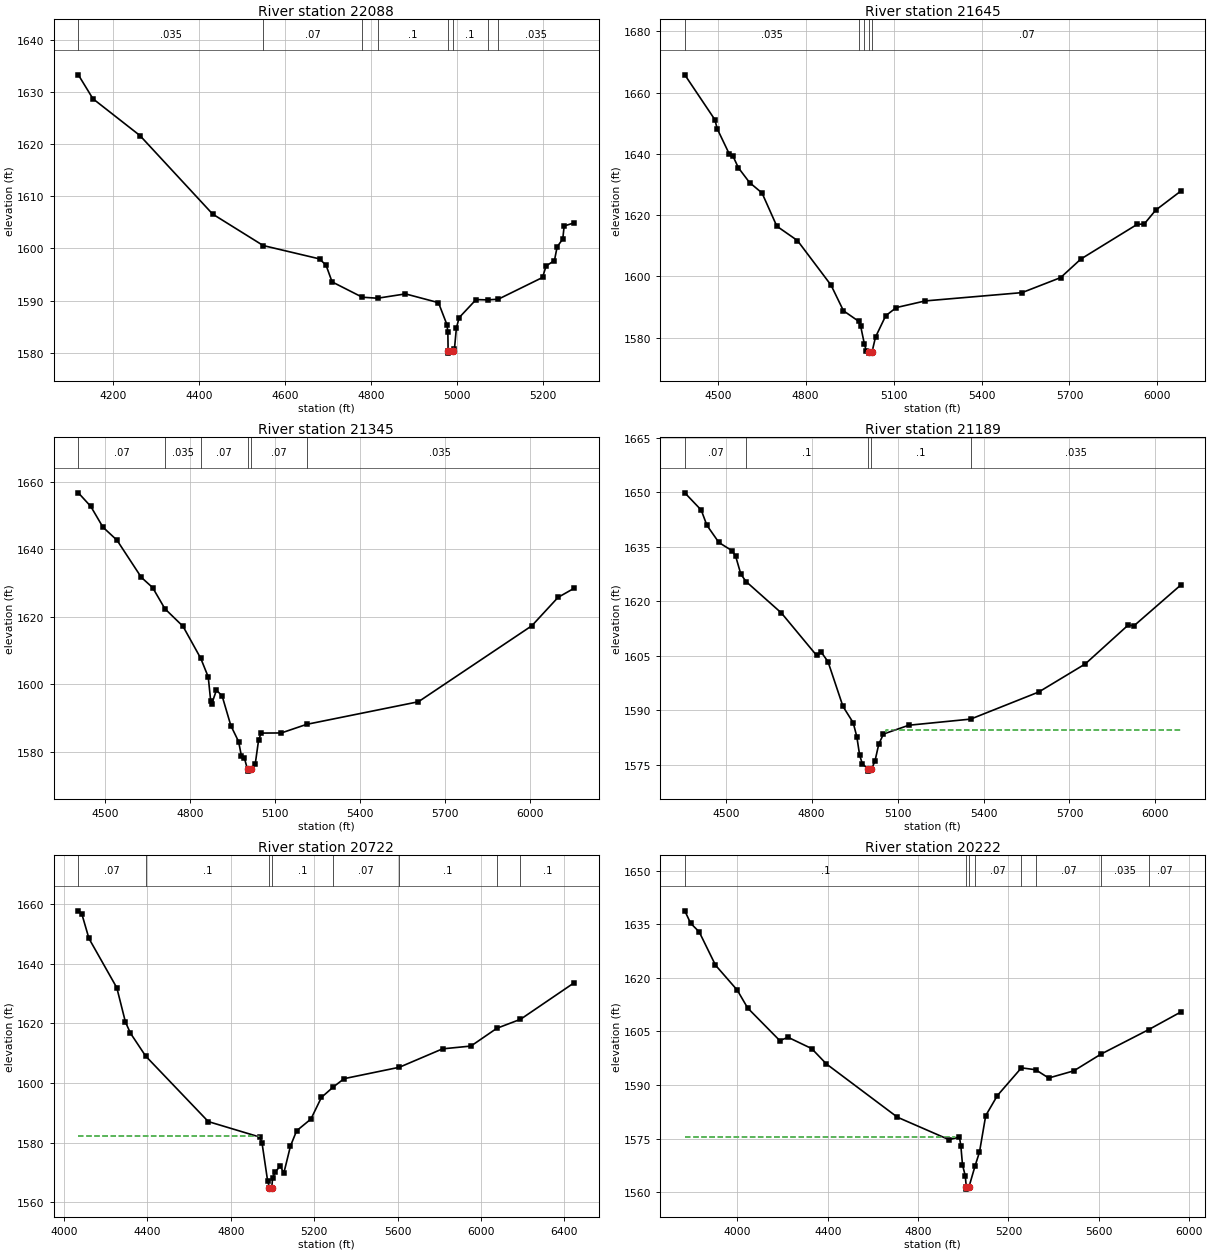
Type RM Length L Ch R = 1 ,22088   ,443,443,443
BEGIN DESCRIPTION:
Bruins Creek 45.0
END DESCRIPTION:
XS GIS Cut Line= 3
      1996074.54      13876863.8        1996525.       13877625.
      1996775.04     13877725.02
#Sta/Elev= 30
  4119.4  1633.3  4153.4 1628.71  4262.7 1621.66  4431.9  1606.6  4549.6 1600.56
  4680.7    1598  4695.9 1596.78  4709.9 1593.59  4780.2 1590.65  4815.8 1590.46
  4880.7 1591.29  4957.4 1589.61  4977.2 1585.38  4979.3 1583.91  4979.9 1580.43
  4980.4 1579.93  4990.6 1580.43  4994.7 1580.78  4999.2 1584.79  5005.7 1586.75
    5045  1590.2  5071.7 1590.14  5096.6 1590.27  5199.6 1594.44  5207.9 1596.64
  5227.3 1597.69  5233.7 1600.34  5246.7  1601.8  5249.9 1604.31  5273.2 1604.91
#Mann= 8 ,-1 , 0
  4119.4    .035       0  4549.6     .07       0  4780.2    .035       0
  4815.8      .1       0  4979.9     .05       0  4990.6      .1       0
  5071.7     .07       0  5096.6    .035       0
Bank Sta=4979.9,4990.6
XS Rating Curve= 0 ,0
Exp/Cntr=0.3,0.1

Type RM Length L Ch R = 1 ,21645   ,300,300,300
BEGIN DESCRIPTION:
Bruins Creek 44.0
END DESCRIPTION:
XS GIS Cut Line= 5
       1995693.8     13877096.07        1996125.       13877525.
        1996275.       13877675.      1996558.85     13877843.85
      1997099.58     13877856.78
#Sta/Elev= 30
  4387.7 1665.77  4490.1 1651.16  4498.6 1648.11  4538.7 1640.08  4551.4 1639.38
  4570.5 1635.43  4608.8  1630.6  4651.1 1627.21  4701.7 1616.36    4772 1611.68
  4886.6 1597.13    4929 1588.76  4980.6 1585.35  4987.4 1583.86  5000.5 1577.85
  5007.5 1575.51  5015.9 1575.44  5016.4 1574.94  5026.7 1575.44  5038.3 1580.17
  5073.2 1587.15  5109.3 1589.81    5208 1591.98  5538.3 1594.69  5669.9 1599.59
  5738.9 1605.65    5931 1616.97    5955 1617.08    5994 1621.59  6079.2 1627.78
#Mann= 5 ,-1 , 0
  4387.7    .035       0  4980.6     .07       0  5000.5     .07       0
  5015.9     .05       0  5026.7     .07       0
Bank Sta=5015.9,5026.7
XS Rating Curve= 0 ,0
Exp/Cntr=0.3,0.1

Type RM Length L Ch R = 1 ,21345   ,156,156,156
BEGIN DESCRIPTION:
Mapping XS a19da700
END DESCRIPTION:
XS GIS Cut Line= 4
      1995392.89      13877642.1       1996198.2     13877817.06
      1996568.42      13877890.3      1997118.78     13877897.21
#Sta/Elev= 30
  4404.8 1656.66  4448.8 1652.64  4491.7 1646.51  4541.4 1642.65  4627.4 1631.66
  4667.3 1628.64  4710.7 1622.38  4774.7 1617.18  4837.4 1607.71  4863.8 1602.21
  4872.5 1595.08  4876.1 1594.24  4892.7 1598.31  4912.9  1596.6  4943.6 1587.84
  4971.2 1583.08    4981 1578.84  4991.1 1578.36  5002.6 1574.87  5003.1 1574.37
  5013.5 1574.87  5029.6 1576.33  5041.8 1583.61    5051 1585.62  5122.2 1585.66
  5211.5  1588.2  5606.3 1594.88  6007.3 1617.36  6099.8 1625.75  6156.7 1628.44
#Mann= 6 ,-1 , 0
  4404.8     .07       0  4710.7    .035       0  4837.4     .07       0
  5002.6     .05       0  5013.5     .07       0  5211.5    .035       0
Bank Sta=5002.6,5013.5
XS Rating Curve= 0 ,0
Exp/Cntr=0.3,0.1

Type RM Length L Ch R = 1 ,21189   ,467,467,467
BEGIN DESCRIPTION:
Bruins Creek 43.0
END DESCRIPTION:
XS GIS Cut Line= 3
      1995347.35     13877786.19        1995975.       13877925.
      1997062.88     13877939.82
#Sta/Elev= 30
  4357.2  1649.9  4414.6 1645.14  4434.2 1640.97  4476.1 1636.22  4522.3 1633.93
  4534.4  1632.5  4552.9 1627.47  4571.1 1625.44  4694.2  1616.8  4817.1  1605.1
  4832.5 1606.08    4857 1603.38  4909.3 1591.03    4945 1586.54  4957.6 1582.71
  4967.6 1577.55  4976.9 1575.24  4997.9 1573.69  4998.4 1573.19  5008.8 1573.69
  5021.1    1576  5034.4 1580.65  5050.7 1583.42  5139.4 1585.84    5355 1587.53
  5592.5 1594.99  5755.2 1602.74  5904.5 1613.42  5925.5 1613.27    6088 1624.45
#Mann= 5 ,-1 , 0
  4357.2     .07       0  4571.1      .1       0  4997.9     .05       0
  5008.8      .1       0    5355    .035       0
#XS Ineff= 2 , 0
                         5060.99         1584.41
Permanent Ineff=
       F       F
Bank Sta=4997.9,5008.8
XS Rating Curve= 0 ,0
Exp/Cntr=0.3,0.1

Type RM Length L Ch R = 1 ,20722   ,500,500,500
BEGIN DESCRIPTION:
Bruins Creek 42.0
END DESCRIPTION:
XS GIS Cut Line= 3
      1995132.53     13878112.82        1996025.       13878375.
      1997423.21     13878747.65
#Sta/Elev= 30
  4069.4  1657.7  4085.9 1656.72  4120.3 1648.43  4253.9 1631.91    4295 1620.47
  4319.1 1616.71    4392 1609.03  4692.5 1587.05  4939.5 1581.86  4949.9    1580
  4977.1 1567.08  4985.8 1564.91  4986.3 1564.41    4997 1564.91  5000.7  1568.2
  5014.5 1570.26  5037.5 1572.14  5054.6 1569.78  5086.5 1578.85  5115.9 1583.96
  5184.6 1587.91  5234.9 1595.16  5290.5 1598.57  5343.6 1601.44  5608.5 1605.26
  5815.5 1611.43  5951.8 1612.37    6076 1618.33  6189.3 1621.34  6446.6 1633.58
#Mann= 8 ,-1 , 0
  4069.4     .07       0    4392      .1       0  4985.8     .05       0
    4997      .1       0  5290.5     .07       0  5608.5      .1       0
    6076    .035       0  6189.3      .1       0
#XS Ineff= 2 , 0
          4936.8 1582.19
Permanent Ineff=
       F       F
Bank Sta=4985.8,4997
XS Rating Curve= 0 ,0
Exp/Cntr=0.3,0.1

Type RM Length L Ch R = 1 ,20222   ,417,417,417
BEGIN DESCRIPTION:
Bruins Creek 41.0
END DESCRIPTION:
XS GIS Cut Line= 3
      1994625.43     13878517.26      1995847.03     13878807.89
      1996771.94     13878973.43
#Sta/Elev= 30
    3767 1638.77  3792.7  1635.3  3830.7 1632.88  3902.9 1623.55  3999.3 1616.55
  4045.5 1611.54  4187.4 1602.43  4224.4 1603.34  4328.9 1600.18    4394 1595.88
  4708.5 1580.96  4936.7 1574.68    4983 1575.39  4989.2 1572.96  4996.5 1567.64
    5009 1564.49  5013.3 1561.32  5013.8 1560.82  5024.6 1561.32  5052.2 1567.32
  5071.8 1571.21  5099.3  1581.4  5151.1 1587.04  5257.3 1594.79  5320.5 1594.26
  5378.1 1591.94  5489.4 1593.95  5609.6 1598.63  5821.3 1605.51  5962.3  1610.4
#Mann= 8 ,-1 , 0
    3767      .1       0  5013.3     .05       0  5024.6      .1       0
  5052.2     .07       0  5257.3    .035       0  5320.5     .07       0
  5609.6    .035       0  5821.3     .07       0
#XS Ineff= 2 , 0
            4963 1575.54
Permanent Ineff=
       F       F
Bank Sta=5013.3,5024.6
XS Rating Curve= 0 ,0
Exp/Cntr=0.3,0.1

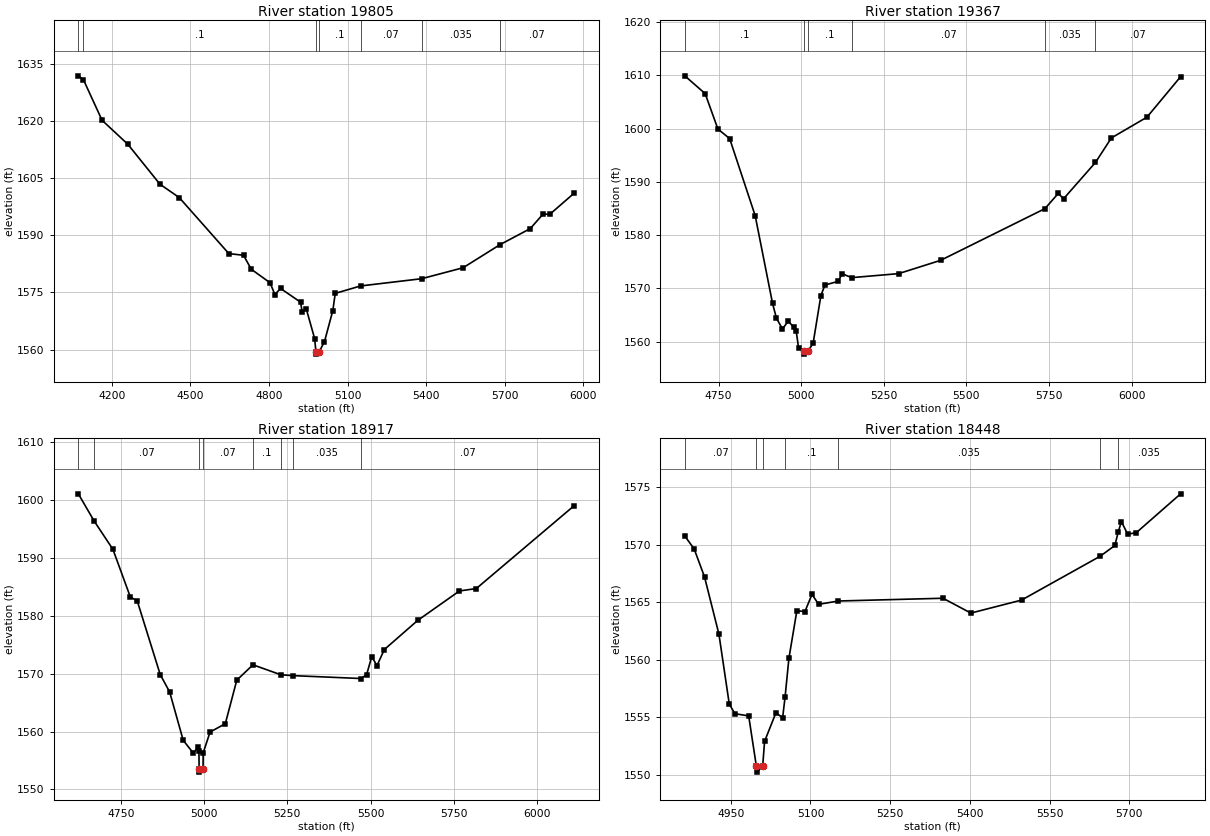
Type RM Length L Ch R = 1 ,19805   ,438,438,438
BEGIN DESCRIPTION:
Bruins Creek 40.0
END DESCRIPTION:
XS GIS Cut Line= 3
      1994717.83     13878927.42        1995625.       13879125.
      1996562.19     13879357.33
#Sta/Elev= 30
  4071.6 1631.94  4091.2  1630.9  4162.2 1620.26  4260.5 1613.97  4383.3 1603.46
    4457 1599.95  4646.5 1585.22  4702.6 1584.78  4732.3  1581.1  4803.9 1577.56
  4822.4 1574.45  4843.9 1576.07  4920.6 1572.45  4926.8 1569.79  4942.1 1570.74
  4974.3 1562.87  4979.4  1559.3  4979.9  1558.8  4990.7  1559.3  5011.9 1562.09
  5043.7 1570.25    5053 1574.77  5149.9 1576.72  5382.9 1578.62  5541.3  1581.5
  5682.8 1587.59  5797.9 1591.79  5847.3 1595.64  5872.1 1595.52  5965.6  1601.1
#Mann= 7 ,-1 , 0
  4071.6     .07       0  4091.2      .1       0  4979.4     .05       0
  4990.7      .1       0  5149.9     .07       0  5382.9    .035       0
  5682.8     .07       0
Bank Sta=4979.4,4990.7
XS Rating Curve= 0 ,0
Exp/Cntr=0.3,0.1

Type RM Length L Ch R = 1 ,19367   ,450,450,450
BEGIN DESCRIPTION:
Bruins Creek 39.0
END DESCRIPTION:
XS GIS Cut Line= 3
      1995105.92     13879350.51        1995425.       13879475.
      1996565.82      13879677.7
#Sta/Elev= 30
  4647.5 1609.91  4709.2 1606.56  4747.8 1599.91  4783.3 1598.12  4860.6 1583.64
  4913.1 1567.18    4925 1564.37  4943.2 1562.36  4960.4 1563.81  4977.9 1562.68
  4984.9 1561.94  4992.1 1558.71  5007.9 1558.13  5008.4 1557.63  5019.7 1558.13
    5036 1559.66  5059.5 1568.61  5071.7 1570.61  5111.3 1571.29    5124 1572.72
    5153    1572  5294.8 1572.75  5422.1 1575.25  5737.9 1584.96  5778.5 1587.84
  5794.1  1586.8  5890.8 1593.63    5939 1598.24  6046.7 1602.14  6148.7 1609.75
#Mann= 6 ,-1 , 0
  4647.5      .1       0  5007.9     .05       0  5019.7      .1       0
    5153     .07       0  5737.9    .035       0  5890.8     .07       0
#XS Ineff= 2 , 0
                         5127.47          1572.4
Permanent Ineff=
       F       F
Bank Sta=5007.9,5019.7
XS Rating Curve= 0 ,0
Exp/Cntr=0.3,0.1

Type RM Length L Ch R = 1 ,18917   ,469,469,469
BEGIN DESCRIPTION:
Bruins Creek 38.0
END DESCRIPTION:
XS GIS Cut Line= 3
      1994917.81     13879542.05        1995175.       13879825.
      1996234.17     13880144.21
#Sta/Elev= 30
  4622.8 1601.09  4669.8 1596.43  4726.7 1591.49  4778.9 1583.26  4799.7 1582.57
  4868.6 1569.86    4897 1566.84  4937.6  1558.5  4967.9 1556.28  4982.8 1557.36
  4984.9 1556.69  4985.4 1553.49  4985.9 1552.99  4997.2 1553.49  4997.6 1556.31
  5018.3 1559.92  5064.1 1561.36  5098.5 1568.88  5147.1 1571.54  5230.6 1569.82
    5267 1569.67  5470.9 1569.17  5488.1  1569.8  5503.8 1572.96  5519.4 1571.39
  5541.4 1574.17  5641.6 1579.21    5767  1584.3  5817.7 1584.72  6111.4 1599.04
#Mann= 8 ,-1 , 0
  4622.8      .1       0  4669.8     .07       0  4985.4     .05       0
  4997.2     .07       0  5147.1      .1       0  5230.6     .07       0
    5267    .035       0  5470.9     .07       0
#XS Ineff= 2 , 0
                         5151.45          1571.2
Permanent Ineff=
       F       F
Bank Sta=4985.4,4997.2
XS Rating Curve= 0 ,0
Exp/Cntr=0.3,0.1

Type RM Length L Ch R = 1 ,18448   ,444,444,444
BEGIN DESCRIPTION:
Bruins Creek 37.0
END DESCRIPTION:
XS GIS Cut Line= 3
      1994874.98     13880124.98        1994975.       13880225.
      1995745.92      13880404.1
#Sta/Elev= 30
  4863.6 1570.77  4881.2 1569.65  4900.7 1567.22  4927.8 1562.24  4947.3 1556.15
  4957.9 1555.32  4983.8 1555.13  4998.3 1550.74  4998.8 1550.24  5010.1 1550.74
  5013.7 1552.91  5035.2 1555.42  5047.6 1554.95  5052.2 1556.74  5059.5 1560.14
  5074.5 1564.29  5089.5 1564.19    5103  1565.7  5115.3 1564.83  5152.6 1565.12
  5349.4 1565.36  5401.9 1564.07  5497.2  1565.2  5645.4 1569.02  5672.8 1569.95
    5679 1571.11  5685.1 1572.02  5696.8 1570.94  5712.8 1571.05  5796.5 1574.44
#Mann= 7 ,-1 , 0
  4863.6     .07       0  4998.3     .05       0  5010.1     .07       0
  5052.2      .1       0  5152.6    .035       0  5645.4     .07       0
    5679    .035       0
Bank Sta=4998.3,5010.1
XS Rating Curve= 0 ,0
Exp/Cntr=0.3,0.1