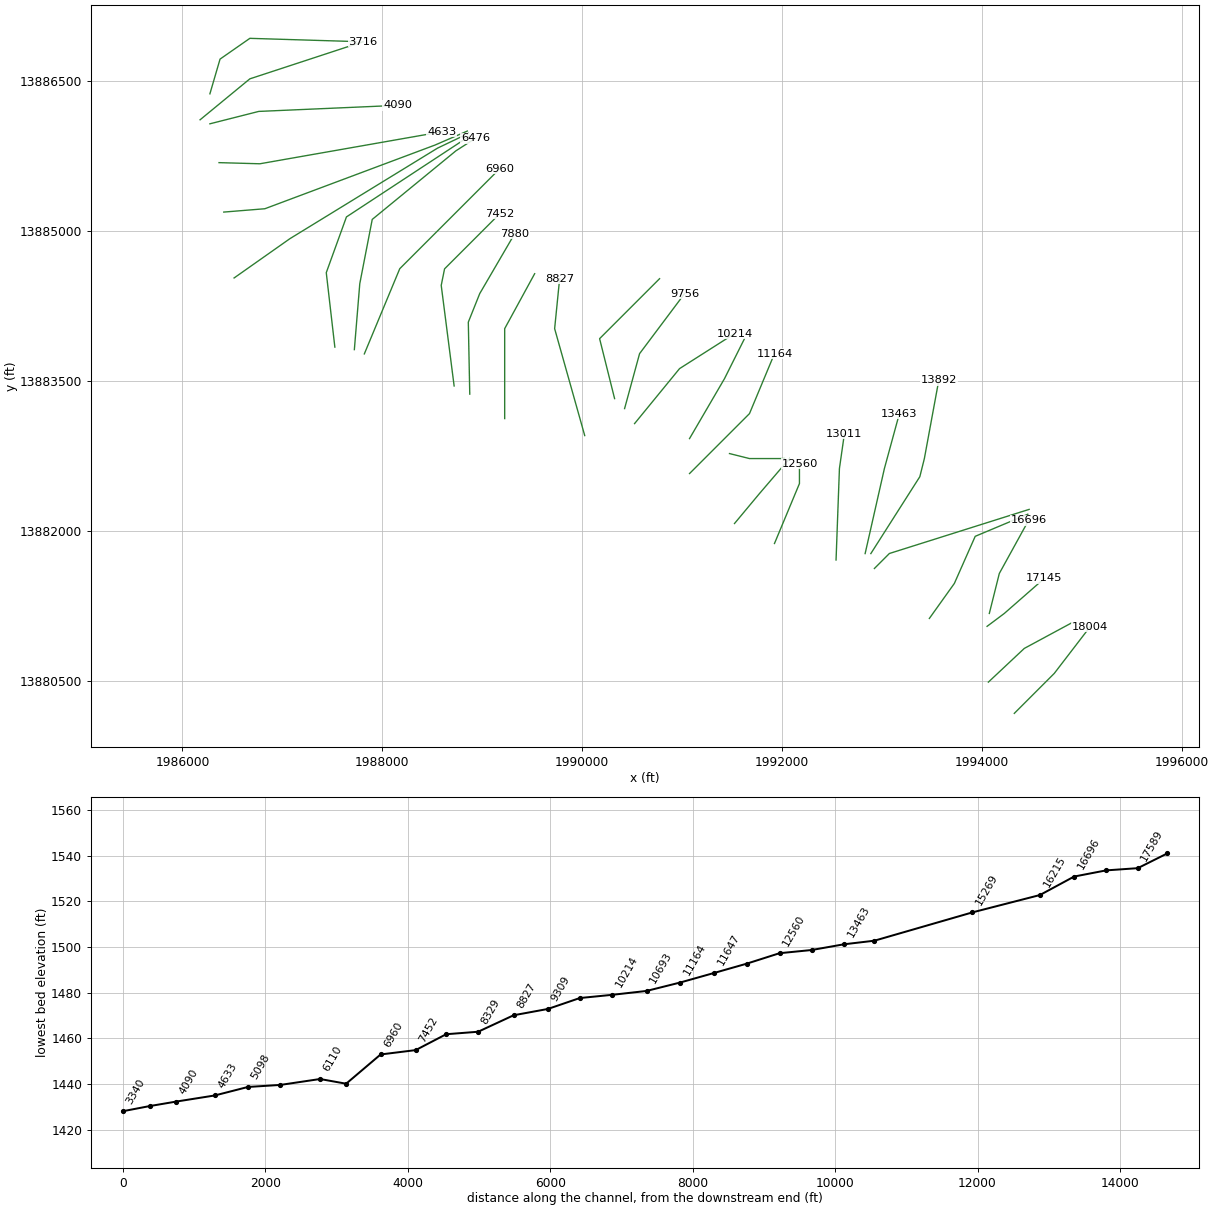
HEC-RAS study Bruins Creek.prj: Bruins Creek Base Level Engineering

--- Bruins Creek.g01 (geometry) --- (continued)

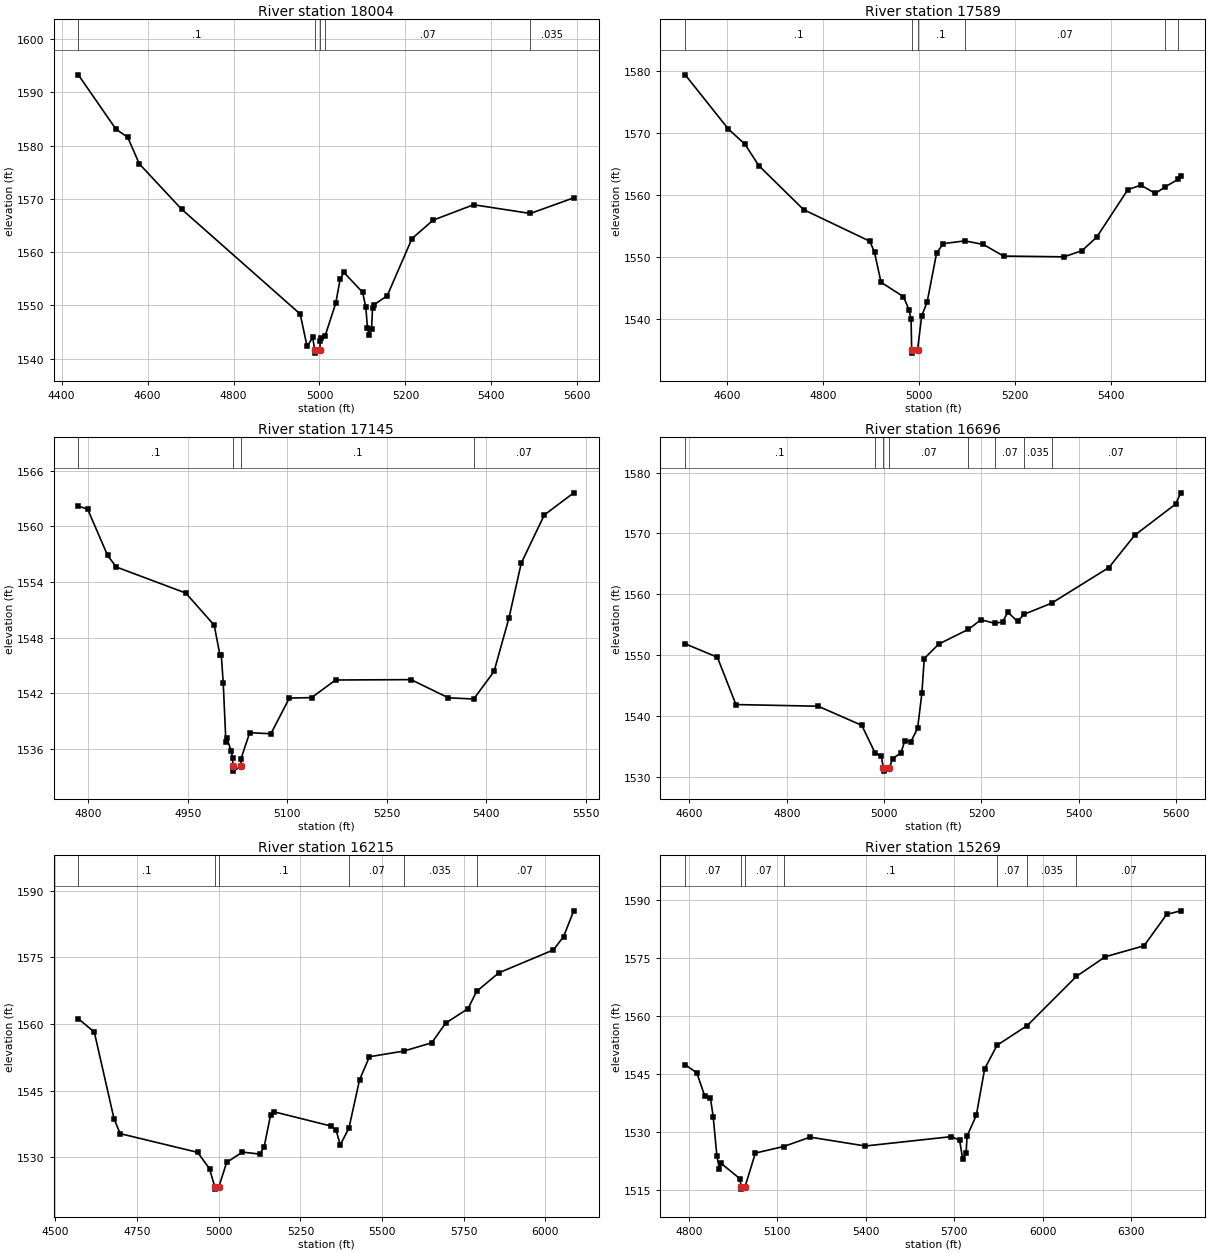
Type RM Length L Ch R = 1 ,18004   ,415,415,415
BEGIN DESCRIPTION:
Bruins Creek 36.0
END DESCRIPTION:
XS GIS Cut Line= 3
      1994324.99     13880174.99        1994725.       13880575.
       1995082.4     13881040.66
#Sta/Elev= 30
  4438.9  1593.3  4526.5 1583.09  4553.7 1581.58  4580.9 1576.57  4679.3 1568.06
  4955.1 1548.38  4971.2 1542.32  4984.3 1543.97    4989 1541.53  4989.5 1541.03
  5000.9 1541.53  5001.7 1543.33  5003.4 1543.84  5012.7 1544.17  5037.7 1550.36
  5048.4    1555  5056.9 1556.18  5100.4 1552.45  5107.9 1549.62  5111.7  1545.7
  5115.5 1544.52  5121.1 1545.51  5123.5 1549.43  5126.8 1550.12  5157.5 1551.79
  5215.3 1562.55  5264.5 1566.01  5358.6  1568.9  5490.7 1567.26  5591.6  1570.2
#Mann= 5 ,-1 , 0
  4438.9      .1       0    4989     .05       0  5000.9      .1       0
  5012.7     .07       0  5490.7    .035       0
#Block Obstruct= 2 , 0
                         5063.23         1555.12
Bank Sta=4989,5000.9
XS Rating Curve= 0 ,0
Exp/Cntr=0.3,0.1

Type RM Length L Ch R = 1 ,17589   ,444,444,444
BEGIN DESCRIPTION:
Bruins Creek 35.0
END DESCRIPTION:
XS GIS Cut Line= 3
       1994065.6     13880487.77        1994425.       13880825.
      1994900.26     13881081.49
#Sta/Elev= 30
  4512.3 1579.41  4602.5 1570.65  4636.8 1568.23  4665.8 1564.77  4759.2 1557.68
  4897.2 1552.59    4907 1550.79  4920.5 1545.98  4967.2 1543.66  4978.8 1541.58
  4983.2 1540.01  4984.4 1535.06  4984.9 1534.56  4996.6 1535.06  5005.4 1540.59
  5016.5 1542.72  5036.3 1550.65  5049.9  1552.2  5095.2 1552.65  5133.8 1552.08
  5175.9  1550.2  5302.1 1550.08  5339.7 1551.08  5370.4 1553.27  5435.1 1560.91
  5462.4 1561.63  5492.5 1560.29  5513.4 1561.38  5540.2 1562.58  5545.2 1563.05
#Mann= 6 ,-1 , 0
  4512.3      .1       0  4984.4     .05       0  4996.6      .1       0
  5095.2     .07       0  5513.4    .035       0  5540.2     .07       0
Bank Sta=4984.4,4996.6
XS Rating Curve= 0 ,0
Exp/Cntr=0.3,0.1

Type RM Length L Ch R = 1 ,17145   ,449,449,449
BEGIN DESCRIPTION:
Bruins Creek 34.0
END DESCRIPTION:
XS GIS Cut Line= 3
       1994052.6     13881045.95        1994225.       13881175.
      1994625.03     13881525.03
#Sta/Elev= 30
  4785.2 1562.19  4799.4 1561.83  4829.4 1556.85  4842.4 1555.61  4947.2  1552.8
  4990.1 1549.33  4998.7 1546.12  5000.8 1546.07  5003.7 1543.06  5007.7 1536.73
  5009.3 1537.12  5015.7 1535.73  5017.8 1535.05  5018.1 1534.09  5018.6 1533.59
  5030.3 1534.09  5030.6 1534.95  5043.6 1537.74  5075.5 1537.62  5103.4 1541.47
  5136.9 1541.52    5173 1543.42  5286.8 1543.46  5343.1  1541.5  5381.3 1541.37
    5412 1544.35  5434.3 1550.07    5453 1556.03  5487.7 1561.22  5532.1 1563.61
#Mann= 4 ,-1 , 0
  4785.2      .1       0  5018.1     .05       0  5030.3      .1       0
  5381.3     .07       0
Bank Sta=5018.1,5030.3
XS Rating Curve= 0 ,0
Exp/Cntr=0.3,0.1

Type RM Length L Ch R = 1 ,16696   ,481,481,481
BEGIN DESCRIPTION:
Bruins Creek 33.0
END DESCRIPTION:
XS GIS Cut Line= 3
        1994075.     13881174.99        1994175.       13881575.
      1994467.17     13882105.43
#Sta/Elev= 30
  4591.4 1551.83  4657.4 1549.63  4695.6 1541.84  4864.5 1541.57  4954.2 1538.42
  4981.1 1533.94  4994.4  1533.3  4998.5 1531.39    4999 1530.89  5010.9 1531.39
  5017.4 1532.96  5034.5 1533.86  5042.3 1535.85  5055.1 1535.76  5068.8 1537.91
  5077.6 1543.67  5082.5 1549.41  5112.3 1551.79  5173.4 1554.22  5198.9 1555.78
    5227 1555.22  5243.3 1555.42  5254.3 1557.03  5274.2 1555.52  5287.7 1556.69
  5344.1 1558.52  5461.9 1564.38  5514.9 1569.69  5599.6 1574.86  5609.3 1576.67
#Mann= 8 ,-1 , 0
  4591.4      .1       0  4981.1     .07       0  4998.5     .05       0
  5010.9     .07       0  5173.4    .035       0    5227     .07       0
  5287.7    .035       0  5344.1     .07       0
Bank Sta=4998.5,5010.9
XS Rating Curve= 0 ,0
Exp/Cntr=0.3,0.1

Type RM Length L Ch R = 1 ,16215   ,946,946,946
BEGIN DESCRIPTION:
Bruins Creek 32.0
END DESCRIPTION:
XS GIS Cut Line= 4
      1993475.01     13881125.01        1993725.       13881475.
      1993933.93     13881946.87      1994459.96     13882167.79
#Sta/Elev= 30
  4569.9 1561.19  4618.9 1558.16  4679.1 1538.67  4697.9 1535.29    4935 1531.07
  4971.7 1527.38  4987.6 1523.28  4988.1 1522.78    5000 1523.28    5024 1528.79
  5072.3 1531.13  5125.7 1530.67  5138.9 1532.34  5158.5 1539.48  5167.8 1540.23
  5342.3 1537.02  5358.8 1536.16  5371.8 1532.73  5398.5 1536.57  5430.9 1547.41
  5461.2 1552.62    5567  1553.9  5652.1 1555.77  5694.5  1560.2  5762.8 1563.44
  5789.3 1567.35  5857.1 1571.52  6024.4 1576.69  6055.6 1579.71  6086.6  1585.5
#Mann= 6 ,-1 , 0
  4569.9      .1       0  4987.6     .05       0    5000      .1       0
  5398.5     .07       0    5567    .035       0  5789.3     .07       0
Bank Sta=4987.6,5000
XS Rating Curve= 0 ,0
Exp/Cntr=0.3,0.1

Type RM Length L Ch R = 1 ,15269   ,1377,1377,1377
BEGIN DESCRIPTION:
Bruins Creek 31.0
END DESCRIPTION:
XS GIS Cut Line= 3
      1992925.01     13881625.01        1993075.       13881775.
      1994473.59     13882216.39
#Sta/Elev= 30
  4787.9 1547.36    4827 1545.29  4854.6 1539.17  4873.3 1538.77  4882.6 1533.96
  4895.3 1523.73  4903.8 1520.42  4909.8 1521.85  4973.4 1517.87  4977.1 1515.69
  4977.6 1515.19  4990.1 1515.69  5025.6 1524.52  5121.2 1526.21  5211.2 1528.64
    5398 1526.35  5689.8 1528.77  5717.7 1527.84    5728 1522.99  5739.7 1524.58
  5742.9  1528.9  5774.3 1534.32  5802.6 1546.34  5844.5 1552.41  5946.9 1557.51
  6113.4 1570.23  6211.1  1575.3  6342.6 1578.15  6419.2 1586.26  6466.6 1587.19
#Mann= 7 ,-1 , 0
  4787.9     .07       0  4977.1     .05       0  4990.1     .07       0
  5121.2      .1       0  5844.5     .07       0  5946.9    .035       0
  6113.4     .07       0
Bank Sta=4977.1,4990.1
XS Rating Curve= 0 ,0
Exp/Cntr=0.3,0.1

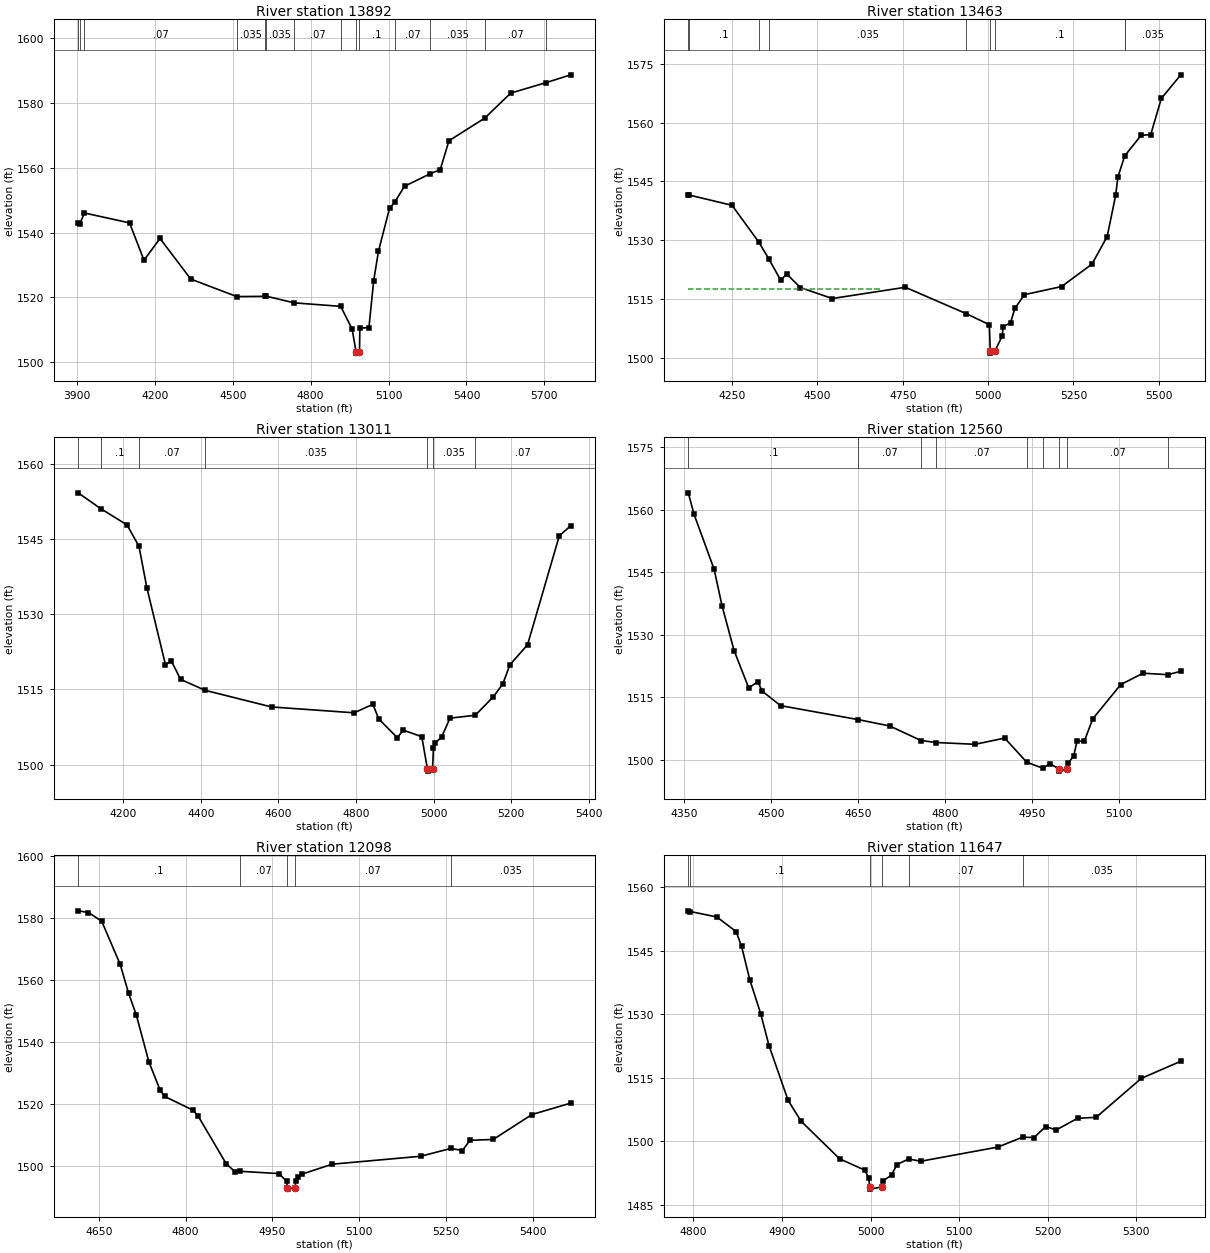
Type RM Length L Ch R = 1 ,13892   ,429,429,429
BEGIN DESCRIPTION:
Bruins Creek 30.0
END DESCRIPTION:
XS GIS Cut Line= 4
      1992889.39     13881774.14      1993379.68     13882543.73
        1993425.       13882725.      1993569.48     13883508.95
#Sta/Elev= 30
  3904.8 1542.82  3910.8 1542.62  3928.7 1546.04  4102.6 1542.98  4158.2 1531.47
    4220 1538.16  4338.5 1525.63  4515.7 1520.23    4625  1520.3  4629.9 1520.33
  4736.7 1518.29  4915.7 1517.21  4959.8 1510.21  4974.7 1503.27  4975.2 1502.77
  4988.1 1503.27  4989.6 1510.46  5024.5 1510.67  5042.8 1525.14  5061.1  1534.2
  5103.8 1547.48    5123  1549.3  5161.6 1554.29  5261.3 1558.18    5299 1559.41
  5332.6 1568.33  5470.4 1575.32  5570.5 1583.05  5707.9 1586.31  5801.3 1588.69
#Mann= 14 ,-1 , 0
  3904.8     .07       0  3910.8      .1       0  3928.7     .07       0
  4515.7    .035       0    4625     .07       0  4629.9    .035       0
  4736.7     .07       0  4915.7      .1       0  4974.7     .05       0
  4988.1      .1       0    5123     .07       0  5261.3    .035       0
  5470.4     .07       0  5707.9    .035       0
Bank Sta=4974.7,4988.1
XS Rating Curve= 0 ,0
Exp/Cntr=0.3,0.1

Type RM Length L Ch R = 1 ,13463   ,452,452,452
BEGIN DESCRIPTION:
Bruins Creek 29.0
END DESCRIPTION:
XS GIS Cut Line= 3
       1992832.2      13881773.9        1993025.       13882625.
      1993174.99     13883174.95
#Sta/Elev= 30
  4121.9 1541.52  4125.4  1541.5  4250.1  1538.9  4328.6 1529.49  4358.2 1525.17
  4392.1 1519.86  4410.7 1521.34  4450.1 1517.92  4543.7 1515.12  4757.7 1517.99
  4935.4 1511.28  5003.8 1508.45  5006.5 1501.69    5007 1501.19  5019.9 1501.69
  5041.2 1505.53  5044.3  1507.9    5066 1508.98  5078.5  1512.6  5106.4  1516.1
  5215.3 1518.17  5304.3 1523.89    5349 1530.94  5373.9  1541.5  5380.2 1546.06
  5400.3  1551.5  5448.5 1556.76  5476.5 1556.94  5507.6 1566.16  5564.6 1572.19
#Mann= 9 ,-1 , 0
  4121.9     .07       0  4125.4      .1       0  4328.6     .07       0
  4358.2    .035       0  4935.4      .1       0  5006.5     .05       0
  5019.9      .1       0  5400.3     .07       0  5400.3    .035       0
#XS Ineff= 2 , 0
            4687 1517.43
Permanent Ineff=
       F       F
Bank Sta=5006.5,5019.9
XS Rating Curve= 0 ,0
Exp/Cntr=0.3,0.1

Type RM Length L Ch R = 1 ,13011   ,451,451,451
BEGIN DESCRIPTION:
Bruins Creek 28.0
END DESCRIPTION:
XS GIS Cut Line= 3
      1992541.25     13881710.13        1992575.       13882625.
      1992624.99     13882974.95
#Sta/Elev= 30
  4084.1 1554.24  4142.3 1551.08    4210 1547.83  4240.8 1543.57  4261.1 1535.29
  4309.1 1519.92  4324.1 1520.68  4348.1    1517  4411.6 1514.81  4582.3  1511.5
  4795.4 1510.33  4843.5 1512.04  4858.5 1509.11  4906.5 1505.36  4921.5 1506.87
  4969.5 1505.57  4983.9 1499.19  4984.4 1498.69  4997.3 1499.19  4999.6 1503.38
  5002.6 1504.27  5020.3 1505.43    5042 1509.26  5107.3 1509.84  5154.1 1513.55
  5178.4 1516.12  5196.5 1519.91    5242 1523.91  5323.8 1545.65  5353.1 1547.66
#Mann= 7 ,-1 , 0
  4084.1    .035       0  4142.3      .1       0  4240.8     .07       0
  4411.6    .035       0  4983.9    .035       0  4997.3    .035       0
  5107.3     .07       0
Bank Sta=4983.9,4997.3
XS Rating Curve= 0 ,0
Exp/Cntr=0.3,0.1

Type RM Length L Ch R = 1 ,12560   ,462,462,462
BEGIN DESCRIPTION:
Bruins Creek 27.0
END DESCRIPTION:
XS GIS Cut Line= 3
        1991925.       13881875.        1992175.       13882475.
        1992175.       13882675.
#Sta/Elev= 30
  4356.9    1564  4366.6 1558.94  4401.5 1545.67  4415.1 1536.94  4435.9  1526.2
  4461.2 1517.23  4477.1 1518.76  4484.1 1516.49  4516.1 1512.99  4650.4 1509.63
  4704.6 1508.11  4758.4 1504.63  4784.6 1504.15  4851.9 1503.72  4902.9 1505.21
  4941.1 1499.42  4969.2 1497.97  4980.9 1499.11  4996.9 1497.79  4997.4 1497.29
  5010.4 1497.79  5012.9 1499.27  5021.9 1500.88  5027.9  1504.5  5040.3 1504.42
  5054.9 1509.82  5103.3 1518.05  5141.9 1520.76  5184.5 1520.41  5206.9 1521.22
#Mann= 9 ,-1 , 0
  4356.9      .1       0  4650.4     .07       0  4758.4      .1       0
  4784.6     .07       0  4941.1    .035       0  4969.2     .07       0
  4996.9     .05       0  5010.4     .07       0  5184.5    .035       0
Bank Sta=4996.9,5010.4
XS Rating Curve= 0 ,0
Exp/Cntr=0.3,0.1

Type RM Length L Ch R = 1 ,12098   ,451,451,451
BEGIN DESCRIPTION:
Bruins Creek 26.0
END DESCRIPTION:
XS GIS Cut Line= 3
      1991525.01     13882075.02        1991775.       13882375.
      1992075.02     13882725.02
#Sta/Elev= 30
  4614.4 1582.43  4632.2 1581.89  4655.1 1579.07  4687.1 1565.16  4701.6 1555.83
  4714.8 1548.92  4736.7 1533.71  4756.2 1524.55    4764 1522.58  4812.7 1518.16
  4821.3 1516.41  4870.2 1500.93  4885.1 1498.35  4893.9 1498.44  4961.8  1497.7
  4974.9 1495.15  4975.9 1493.19  4976.4 1492.69  4989.5 1493.19  4990.5 1495.17
  4993.8 1496.46  5002.2 1497.58  5053.6 1500.73  5206.6 1503.29  5258.8 1505.81
  5278.8 1505.14  5291.7 1508.43  5332.1 1508.71  5398.9 1516.74  5465.9 1520.42
#Mann= 5 ,-1 , 0
  4614.4      .1       0  4893.9     .07       0  4975.9     .05       0
  4989.5     .07       0  5258.8    .035       0
Bank Sta=4975.9,4989.5
XS Rating Curve= 0 ,0
Exp/Cntr=0.3,0.1

Type RM Length L Ch R = 1 ,11647   ,483,483,483
BEGIN DESCRIPTION:
Bruins Creek 25.0
END DESCRIPTION:
XS GIS Cut Line= 3
      1991475.03     13882774.99        1991675.       13882725.
      1992024.98       13882725.
#Sta/Elev= 30
  4794.2 1554.47  4796.5 1554.31  4826.5 1553.01  4848.2 1549.56  4854.4 1546.04
  4863.6  1538.2    4876 1530.12  4885.3 1522.62  4906.9 1509.66  4921.5 1504.75
  4965.1 1495.84  4993.5 1493.17  4998.1 1491.23  4998.9 1489.18  4999.4 1488.68
  5012.5 1489.18  5013.7 1490.56  5023.7 1492.01  5029.7 1494.48    5043 1495.81
  5056.7 1495.27  5143.7 1498.62  5171.6 1500.96  5184.7 1500.88  5197.7 1503.46
  5209.7 1502.67  5233.7 1505.43  5254.7 1505.65  5305.7 1514.86  5350.3 1518.91
#Mann= 6 ,-1 , 0
  4794.2     .07       0  4796.5      .1       0  4998.9     .05       0
  5012.5      .1       0    5043     .07       0  5171.6    .035       0
Bank Sta=4998.9,5012.5
XS Rating Curve= 0 ,0
Exp/Cntr=0.3,0.1

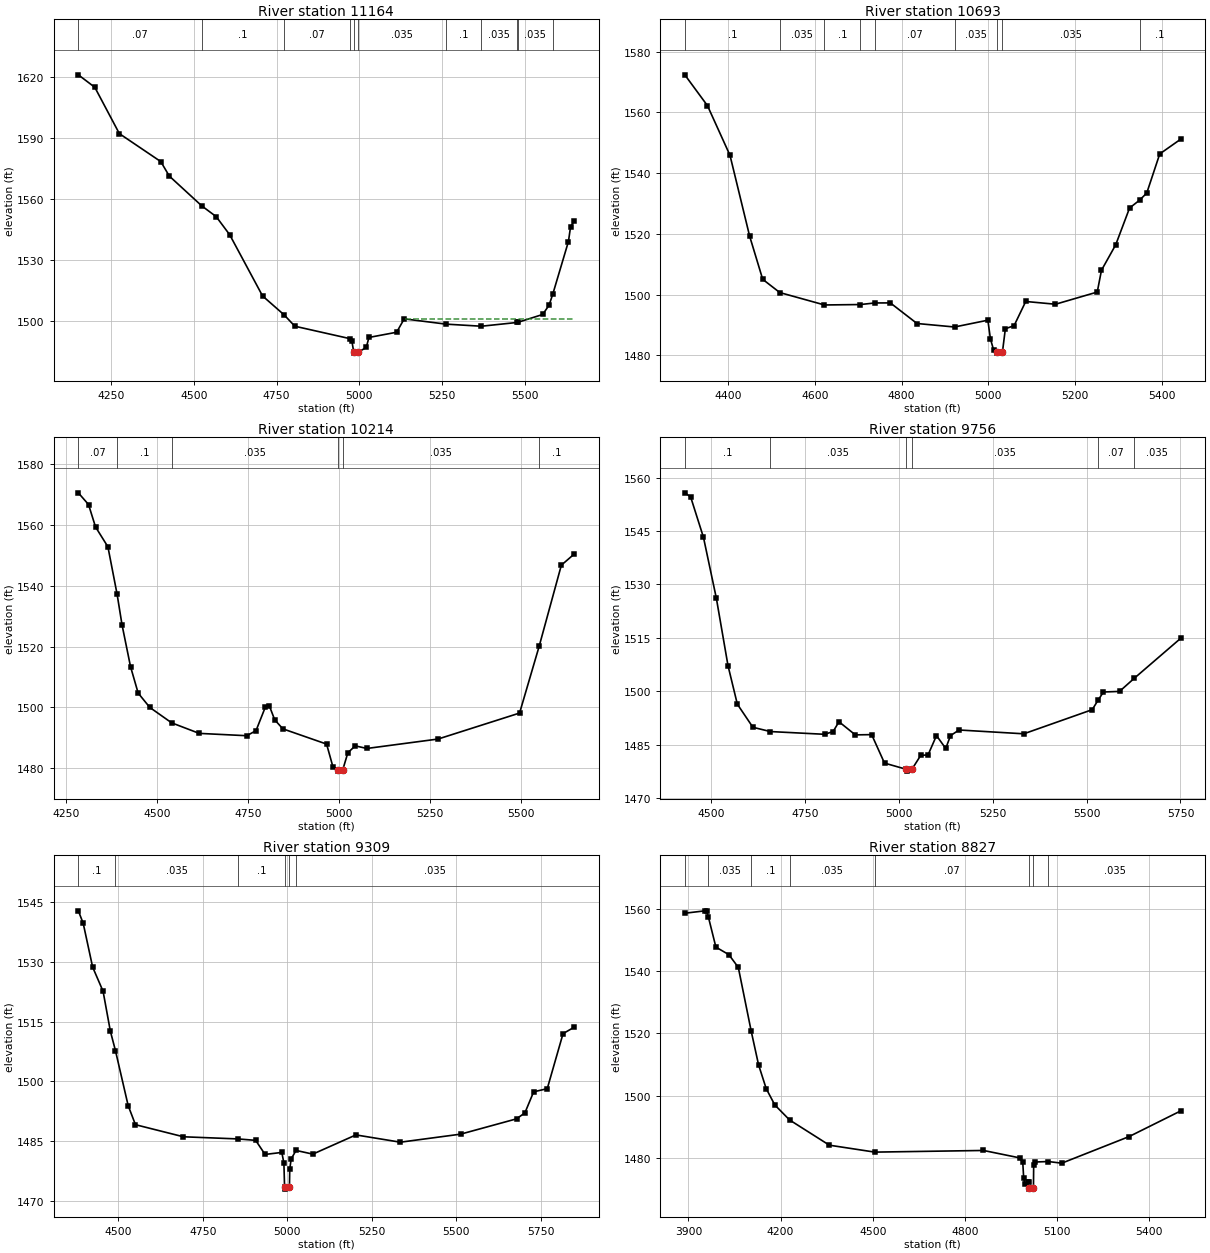
Type RM Length L Ch R = 1 ,11164   ,471,471,471
BEGIN DESCRIPTION:
Bruins Creek 24.0
END DESCRIPTION:
XS GIS Cut Line= 3
        1991075.       13882575.        1991675.       13883175.
      1991924.99     13883774.97
#Sta/Elev= 30
  4150.6 1621.29  4200.4 1615.15  4274.6 1592.37  4399.8 1578.62  4425.5 1571.51
  4523.8 1556.82  4567.3 1551.55    4608 1542.66  4707.4 1512.55  4772.7 1503.22
  4804.9 1497.66  4971.2 1491.56  4977.1 1490.54    4983 1484.93  4983.5 1484.43
  4996.6 1484.93  5020.8  1487.2  5028.8 1492.14  5112.6  1494.7  5135.5 1501.29
  5261.7 1498.69  5368.8 1497.66  5476.8 1499.51  5478.3 1499.54  5553.8 1503.43
  5573.3 1507.99  5584.8  1513.6  5631.8 1539.32  5638.3 1546.67  5649.1 1549.24
#Mann= 11 ,-1 , 0
  4150.6     .07       0  4523.8      .1       0  4772.7     .07       0
  4971.2    .035       0    4983    .035       0  4996.6    .035       0
  5261.7      .1       0  5368.8    .035       0  5476.8      .1       0
  5478.3    .035       0  5584.8     .07       0
#XS Ineff= 2 , 0
                         5137.85         1501.31
Permanent Ineff=
       F       F
Bank Sta=4983,4996.6
XS Rating Curve= 0 ,0
Exp/Cntr=0.3,0.1

Type RM Length L Ch R = 1 ,10693   ,479,479,479
BEGIN DESCRIPTION:
Bruins Creek 23.0
END DESCRIPTION:
XS GIS Cut Line= 3
      1991075.01     13882925.02        1991425.       13883525.
      1991624.99     13883924.99
#Sta/Elev= 30
  4300.8 1572.34    4353 1562.19  4404.9 1545.83  4450.1 1519.25  4480.2 1505.04
  4519.6 1500.68  4622.5  1496.6  4705.1 1496.74  4738.5 1497.26  4774.1 1497.28
  4835.5  1490.5  4921.9 1489.35  4998.7 1491.59  5004.6 1485.45  5012.1 1481.71
  5018.7 1481.25  5019.2 1480.75  5032.4 1481.25    5039 1488.77  5059.1 1489.79
  5085.9 1497.75  5154.4 1496.84  5250.6 1500.85  5260.3 1508.02  5293.1  1516.4
    5325  1528.5  5348.2 1531.11  5364.6 1533.43  5394.5 1546.31  5442.6 1551.14
#Mann= 9 ,-1 , 0
  4300.8      .1       0  4519.6    .035       0  4622.5      .1       0
  4705.1    .035       0  4738.5     .07       0  4921.9    .035       0
  5018.7    .035       0  5032.4    .035       0  5348.2      .1       0
Bank Sta=5018.7,5032.4
XS Rating Curve= 0 ,0
Exp/Cntr=0.3,0.1

Type RM Length L Ch R = 1 ,10214   ,458,458,458
BEGIN DESCRIPTION:
Bruins Creek 22.0
END DESCRIPTION:
XS GIS Cut Line= 3
      1990525.01     13883075.01        1990975.       13883625.
      1991524.96     13883974.98
#Sta/Elev= 30
  4283.9 1570.55  4311.9  1566.7  4331.1 1559.35  4365.2  1552.8  4390.5 1537.17
    4404 1527.13  4427.3 1513.43  4448.3 1504.71  4480.3    1500  4540.4 1494.93
  4616.1 1491.47  4746.8  1490.7  4772.2 1492.37  4797.9 1500.15  4808.6 1500.58
  4823.5 1495.93  4845.9 1492.96  4966.1 1487.95  4983.4 1480.52  4996.9 1479.56
  4997.4 1479.06  5010.7 1479.56  5024.5 1485.09  5044.8 1487.37  5076.8 1486.51
  5272.4 1489.61  5496.4 1498.15  5550.2  1520.1  5611.2 1546.77  5646.4 1550.41
#Mann= 6 ,-1 , 0
  4283.9     .07       0  4390.5      .1       0  4540.4    .035       0
  4996.9    .035       0  5010.7    .035       0  5550.2      .1       0
Bank Sta=4996.9,5010.7
XS Rating Curve= 0 ,0
Exp/Cntr=0.3,0.1

Type RM Length L Ch R = 1 ,9756    ,447,447,447
BEGIN DESCRIPTION:
Bruins Creek 21.0
END DESCRIPTION:
XS GIS Cut Line= 3
      1990424.99     13883224.98        1990575.       13883775.
      1991024.99     13884374.99
#Sta/Elev= 30
  4430.3 1555.71  4445.8 1554.58    4480 1543.22  4514.3 1526.15  4545.3 1507.24
  4570.2 1496.42  4611.6 1489.94  4658.1 1488.74  4802.8 1487.97  4825.2 1488.75
  4840.8 1491.49  4884.3 1487.81  4927.8 1487.88    4962 1479.89  5020.5 1478.14
    5021 1477.64  5034.9 1478.14  5058.5 1482.07  5077.9 1482.18  5100.4 1487.61
    5125    1484  5137.7 1487.59  5160.4 1489.18  5332.9 1488.11    5515 1494.88
  5530.9 1497.59    5545 1499.84  5587.7    1500  5626.7 1503.66  5750.4 1514.88
#Mann= 6 ,-1 , 0
  4430.3      .1       0  4658.1    .035       0  5020.5    .035       0
  5034.9    .035       0  5530.9     .07       0  5626.7    .035       0
Bank Sta=5020.5,5034.9
XS Rating Curve= 0 ,0
Exp/Cntr=0.3,0.1

Type RM Length L Ch R = 1 ,9309    ,482,482,482
BEGIN DESCRIPTION:
Bruins Creek 20.0
END DESCRIPTION:
XS GIS Cut Line= 3
      1990325.01     13883324.97        1990175.       13883925.
      1990774.98     13884524.98
#Sta/Elev= 30
  4381.4 1542.83  4395.8 1539.69  4423.7 1528.69  4454.6  1522.6  4476.2 1512.55
  4491.2 1507.69  4528.8 1493.87  4550.4 1489.06  4692.5 1486.02  4854.2 1485.48
  4906.1 1485.12  4933.9 1481.58  4983.4 1482.09  4989.6 1479.42  4991.6 1473.36
  4992.1 1472.86    5006 1473.36  5006.9 1477.87  5011.2 1480.47  5025.6 1482.59
  5075.1 1481.66  5202.7 1486.49  5334.2 1484.66  5512.4 1486.68  5677.9 1490.53
  5702.7 1492.04  5728.5 1497.32  5768.8 1498.12  5815.5 1511.95  5848.4 1513.57
#Mann= 6 ,-1 , 0
  4381.4      .1       0  4491.2    .035       0  4854.2      .1       0
  4991.6     .05       0    5006      .1       0  5025.6    .035       0
Bank Sta=4991.6,5006
XS Rating Curve= 0 ,0
Exp/Cntr=0.3,0.1

Type RM Length L Ch R = 1 ,8827    ,498,498,498
BEGIN DESCRIPTION:
Bruins Creek 19.0
END DESCRIPTION:
XS GIS Cut Line= 3
      1990026.12     13882954.88        1989725.       13884025.
        1989775.     13884525.02
#Sta/Elev= 30
  3888.3 1558.57  3953.8 1559.34  3960.1 1559.16  3965.3 1557.28  3989.5 1547.71
  4031.8 1545.28  4062.5  1541.2  4104.6 1520.69  4128.4 1509.97  4153.3 1502.32
  4181.3 1497.09  4229.6 1492.26    4359 1484.18  4506.8 1481.96  4860.7 1482.49
  4979.2  1480.1  4988.5  1478.8  4991.5 1473.78  4994.8 1471.74    5007 1472.46
  5008.5 1472.22  5008.7 1470.59  5009.2 1470.09  5023.4 1470.59  5024.1 1477.71
  5027.7 1478.78  5071.7 1478.94  5115.5 1478.41  5334.7 1486.94  5502.5 1495.16
#Mann= 8 ,-1 , 0
  3888.3     .07       0  3965.3    .035       0  4104.6      .1       0
  4229.6    .035       0  4506.8     .07       0  5008.7     .05       0
  5023.4     .07       0  5071.7    .035       0
Bank Sta=5008.7,5023.4
XS Rating Curve= 0 ,0
Exp/Cntr=0.3,0.1

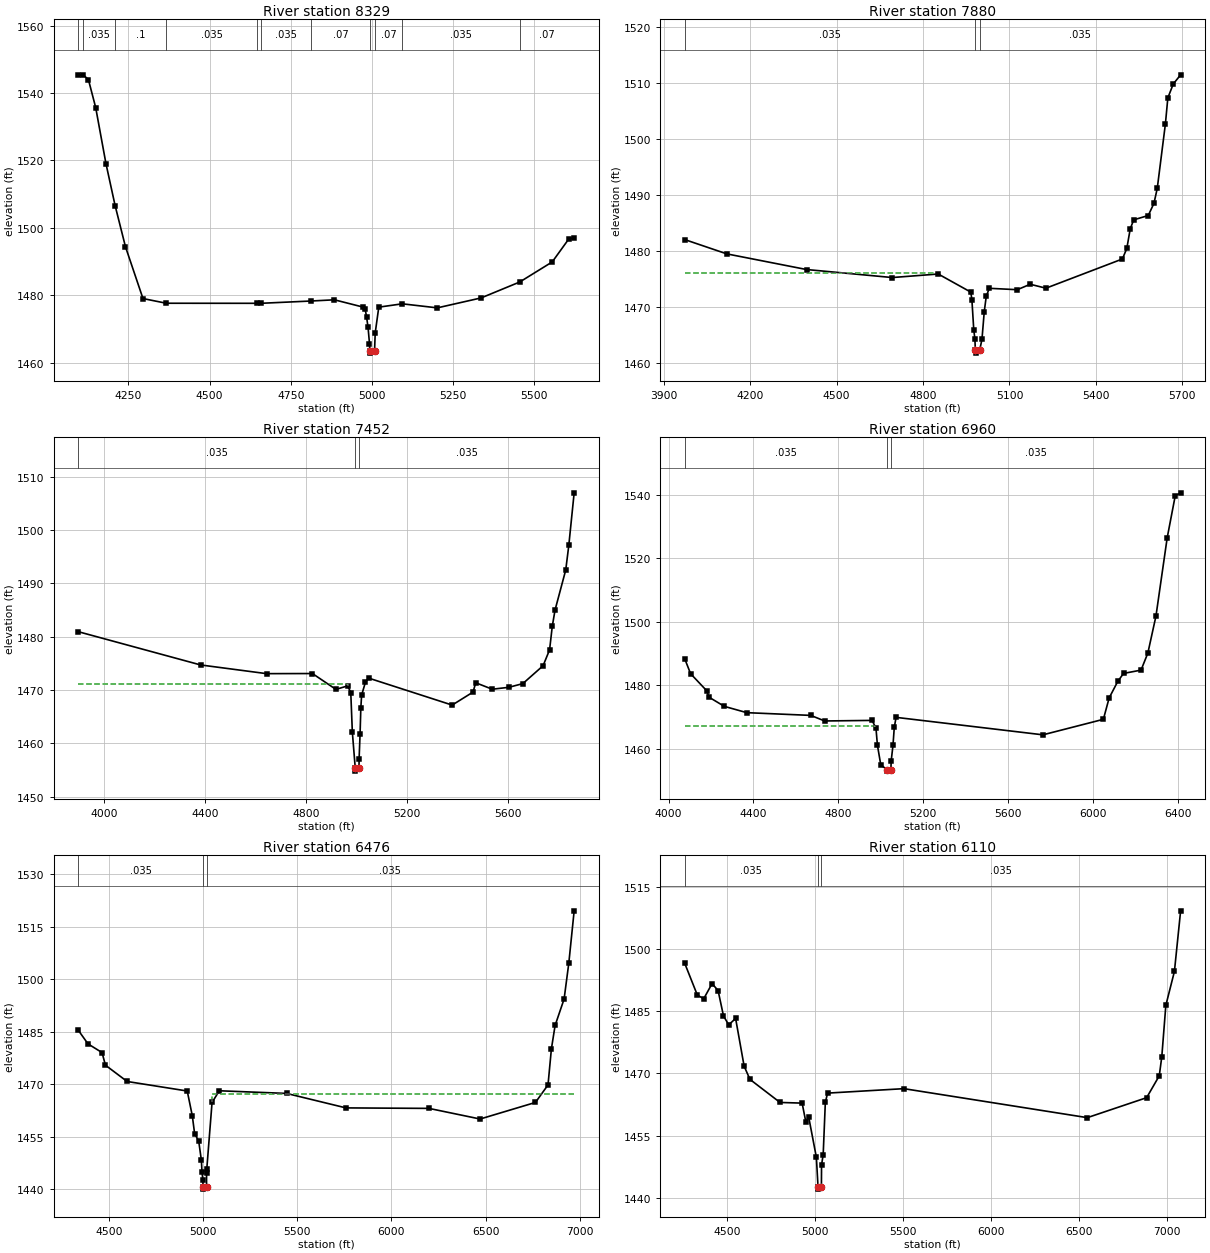
Type RM Length L Ch R = 1 ,8329    ,449,449,449
BEGIN DESCRIPTION:
Bruins Creek 18.0
END DESCRIPTION:
XS GIS Cut Line= 3
        1989225.     13883124.98        1989225.       13884025.
      1989524.99     13884574.98
#Sta/Elev= 30
  4096.1  1545.3  4110.9 1545.38  4127.1 1543.98  4149.5 1535.69  4181.1 1519.08
  4209.3 1506.62  4241.1 1494.45  4295.1 1479.05  4366.9 1477.66  4645.1 1477.64
  4659.8 1477.65  4812.6 1478.32  4884.5 1478.68  4973.1 1476.51  4979.1 1475.94
  4983.5 1473.61  4988.1 1470.47  4992.5 1465.71  4993.3 1463.37  4993.8 1462.87
    5008 1463.37  5010.1 1468.87  5021.1  1476.5  5093.4 1477.49  5201.3 1476.29
  5336.2 1479.24  5455.1 1483.96  5555.1 1489.91  5605.5 1496.64  5622.6 1497.05
#Mann= 11 ,-1 , 0
  4096.1     .07       0  4110.9    .035       0  4209.3      .1       0
  4366.9    .035       0  4645.1     .07       0  4659.8    .035       0
  4812.6     .07       0  4993.3     .05       0    5008     .07       0
  5093.4    .035       0  5455.1     .07       0
Bank Sta=4993.3,5008
XS Rating Curve= 0 ,0
Exp/Cntr=0.3,0.1

Type RM Length L Ch R = 1 ,7880    ,428,428,428
BEGIN DESCRIPTION:
Bruins Creek 17.0
END DESCRIPTION:
XS GIS Cut Line= 4
      1988875.62     13883369.92      1988861.12      13884090.3
        1988975.       13884375.      1989325.01     13884975.02
#Sta/Elev= 30
  3972.6 1482.04  4118.7 1479.49  4395.4  1476.7  4693.1 1475.27  4852.7  1475.9
  4965.8 1472.67  4969.6 1471.29    4976 1465.98    4980 1464.29  4981.6 1462.28
  4982.1 1461.78  4996.4 1462.28  5004.5 1464.22  5012.5 1469.19  5019.4  1471.9
  5029.8 1473.35  5127.1  1473.1  5172.2 1474.07  5226.7 1473.37  5492.1 1478.58
  5507.5 1480.46  5519.5 1483.98  5531.6 1485.57    5582 1486.34  5601.8 1488.52
  5613.3  1491.2  5641.6 1502.72    5650 1507.33  5668.9 1509.82  5694.4 1511.45
#Mann= 3 ,-1 , 0
  3972.6    .035       0  4981.6     .05       0  4996.4    .035       0
#XS Ineff= 2 , 0
         4837.07 1476.04
Permanent Ineff=
       F       F
Bank Sta=4981.6,4996.4
XS Rating Curve= 0 ,0
Exp/Cntr=0.3,0.1

Type RM Length L Ch R = 1 ,7452    ,492,492,492
BEGIN DESCRIPTION:
Bruins Creek 16.0
END DESCRIPTION:
XS GIS Cut Line= 4
       1988719.2     13883451.55      1988590.03     13884457.91
      1988623.33     13884623.33      1989174.97     13885174.97
#Sta/Elev= 30
  3898.4 1480.95  4382.6 1474.72  4643.9 1473.09  4825.4 1473.11  4918.5 1470.14
  4965.1  1470.8  4977.3 1469.53  4983.5 1462.14  4995.1 1455.32  4995.6 1454.82
  5009.9 1455.32  5010.2 1457.02  5014.1 1461.78  5017.1 1466.63  5020.2 1469.05
  5035.5 1471.52  5047.7 1472.26  5378.8  1467.2  5461.3 1469.63  5472.2 1471.38
  5537.6 1470.17  5603.1 1470.53  5658.6 1471.22  5738.9 1474.58  5764.6 1477.56
  5775.2 1481.95  5786.1 1484.99  5828.6 1492.53  5840.7 1497.14  5861.9 1506.98
#Mann= 3 ,-1 , 0
  3898.4    .035       0  4995.1     .05       0  5009.9    .035       0
#XS Ineff= 2 , 0
         4965.84 1471.22
Permanent Ineff=
       F       F
Bank Sta=4995.1,5009.9
XS Rating Curve= 0 ,0
Exp/Cntr=0.3,0.1

Type RM Length L Ch R = 1 ,6960    ,484,484,484
BEGIN DESCRIPTION:
Bruins Creek 15.0
END DESCRIPTION:
XS GIS Cut Line= 3
      1987820.54     13883772.38        1988175.       13884625.
      1989174.94     13885624.94
#Sta/Elev= 30
  4076.6  1488.3  4103.7 1483.66  4179.2 1478.31  4191.4 1476.21  4262.9 1473.34
  4368.8 1471.35  4670.3 1470.49  4736.1 1468.73  4959.5 1468.91  4977.8 1466.48
  4984.7 1461.08  5000.5  1454.9  5029.2 1453.41  5029.7 1452.91  5048.2 1453.41
  5049.5  1456.1    5058    1461  5064.1 1466.68  5072.6 1469.87    5765 1464.36
  6049.9 1469.25  6077.2 1476.01  6117.8 1481.21    6145 1483.73  6227.5 1484.77
  6259.6 1490.15  6297.8 1501.81  6350.8 1526.52  6388.7 1539.76  6414.1 1540.69
#Mann= 3 ,-1 , 0
  4076.6    .035       0  5029.2     .05       0  5048.2    .035       0
#XS Ineff= 2 , 0
         4975.32 1467.05
Permanent Ineff=
       F       F
Bank Sta=5029.2,5048.2
XS Rating Curve= 0 ,0
Exp/Cntr=0.3,0.1

Type RM Length L Ch R = 1 ,6476    ,366,366,366
BEGIN DESCRIPTION:
Bruins Creek 14.0
END DESCRIPTION:
XS GIS Cut Line= 5
      1987720.64     13883815.26        1987775.       13884475.
       1987899.6     13885118.08      1988737.16     13885804.75
      1988932.23     13885930.01
#Sta/Elev= 30
  4338.5 1485.41  4389.8 1481.54  4464.3 1479.06  4482.4 1475.46  4597.5 1470.81
  4916.6 1468.09  4943.6 1460.98  4955.7 1455.94  4977.4 1453.82  4991.8 1448.27
  4994.8 1444.95  4999.6 1442.77    5000 1440.59  5000.5 1440.09  5019.1 1440.59
  5019.2 1444.82  5020.2 1445.75  5048.3 1464.82  5086.7 1468.16  5443.9  1467.4
  5759.5 1463.27  6199.7 1463.13  6471.2  1460.1    6765 1464.83  6831.6 1469.83
  6849.6 1480.12  6869.2 1486.79  6917.1 1494.36  6942.1 1504.64  6970.4 1519.51
#Mann= 3 ,-1 , 0
  4338.5    .035       0    5000     .05       0  5019.1    .035       0
#XS Ineff= 2 , 0
                         5049.33          1467.3
Permanent Ineff=
       F       F
#Block Obstruct= 2 , 0
                         5358.74         1467.09
Bank Sta=5000,5019.1
XS Rating Curve= 0 ,0
Exp/Cntr=0.3,0.1

Type RM Length L Ch R = 1 ,6110    ,558,558,558
BEGIN DESCRIPTION:
Bruins Creek 13.0
END DESCRIPTION:
XS GIS Cut Line= 4
      1987525.49     13883840.32      1987439.64     13884585.39
      1987641.57     13885143.19      1988874.87     13885953.12
#Sta/Elev= 30
  4259.9 1496.48  4331.4 1488.85  4367.7    1488  4414.9 1491.64  4449.2 1489.96
  4479.8 1483.86  4509.6 1481.71  4548.8 1483.25  4597.2 1471.75  4630.4 1468.57
  4801.3 1463.02  4926.9 1462.86  4947.5 1458.42  4964.5 1459.45  5007.9  1449.8
  5017.3 1442.65  5017.8 1442.15  5036.5 1442.65  5037.3 1447.99  5046.6 1450.44
  5058.8 1463.03  5071.6 1465.27  5505.5 1466.34  6548.1 1459.36  6885.4 1464.17
  6957.2 1469.44  6971.6 1474.06  6994.5 1486.39  7043.3 1494.57  7078.6 1509.16
#Mann= 3 ,-1 , 0
  4259.9    .035       0  5017.3     .05       0  5036.5    .035       0
#Block Obstruct= 2 , 0
                         5510.65         1466.09
Bank Sta=5017.3,5036.5
XS Rating Curve= 0 ,0
Exp/Cntr=0.3,0.1

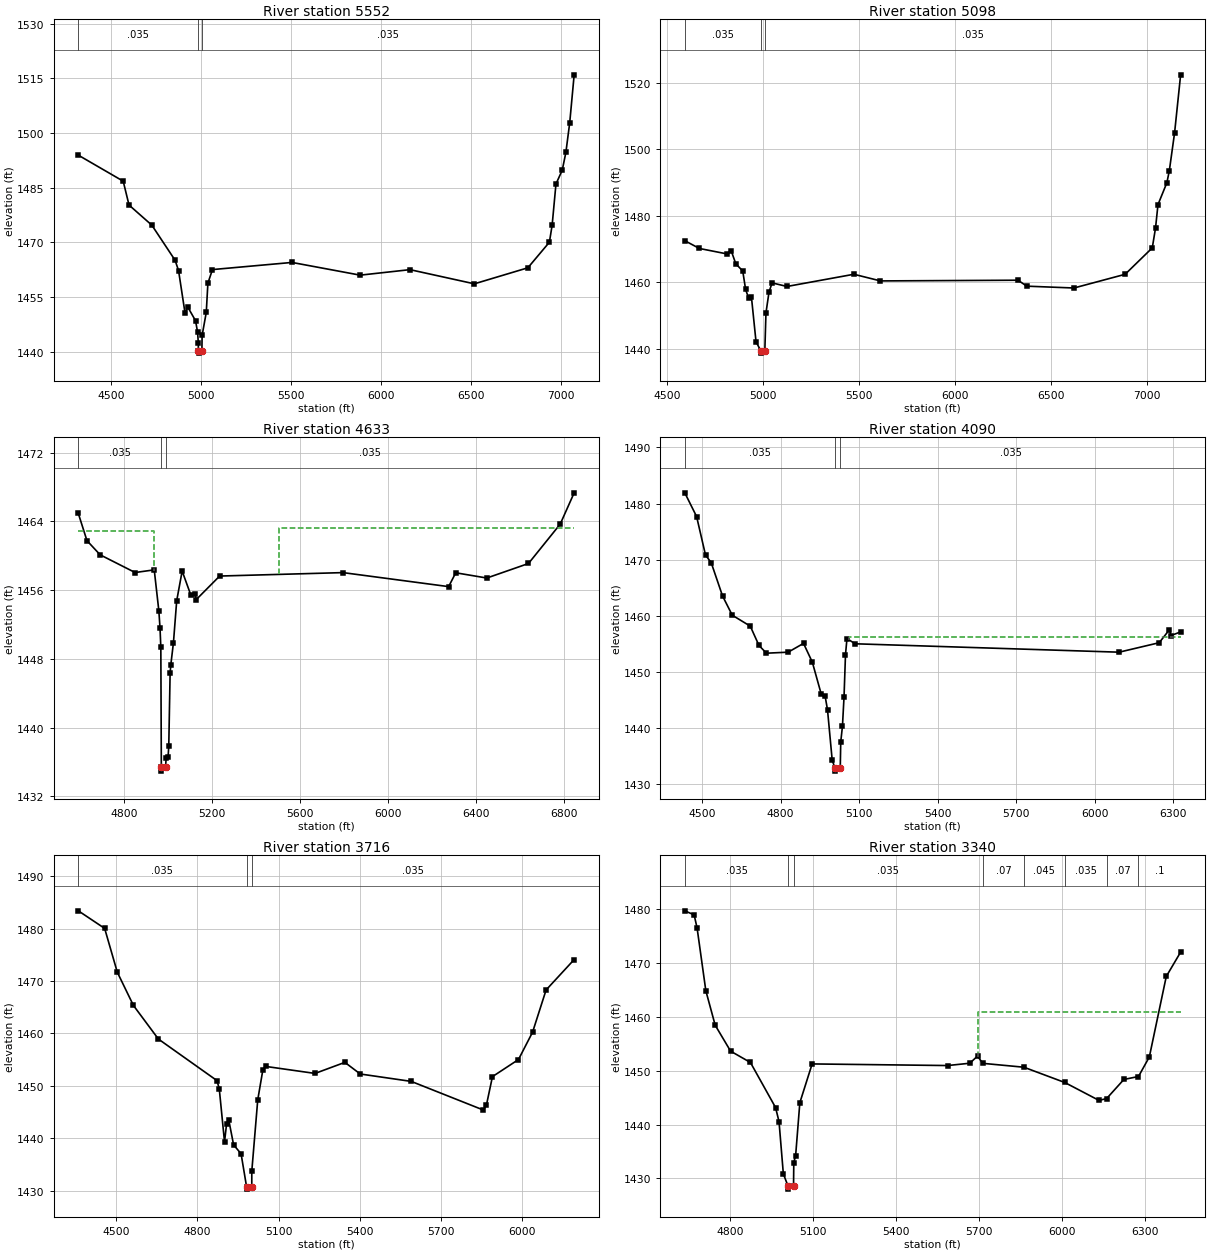
Type RM Length L Ch R = 1 ,5552    ,454,454,454
BEGIN DESCRIPTION:
Bruins Creek 12.0
END DESCRIPTION:
XS GIS Cut Line= 4
      1986517.13     13884532.22        1987075.       13884925.
      1988553.26     13885831.62      1988861.73     13885979.06
#Sta/Elev= 30
  4317.6 1493.89  4567.2 1486.75  4599.6  1480.2  4726.5 1474.68  4855.7 1465.06
  4875.1 1462.23  4911.5 1450.44  4926.7 1452.18  4969.8 1448.44  4981.2 1445.24
  4984.9 1442.44  4985.6 1440.06  4986.1 1439.56  5004.9 1440.06  5006.3 1444.45
  5029.3 1450.73  5038.3 1458.75  5063.7 1462.49  5506.3 1464.45  5885.6 1460.96
  6162.6 1462.47  6520.7 1458.58  6818.4 1462.98  6938.1    1470  6953.4 1474.67
  6974.7 1485.98  7009.6 1489.77  7029.8 1494.63  7051.2 1502.79  7075.9 1515.94
#Mann= 3 ,-1 , 0
  4317.6    .035       0  4985.6     .05       0  5004.9    .035       0
#Block Obstruct= 2 , 0
                         5506.73         1464.62
Bank Sta=4985.6,5004.9
XS Rating Curve= 0 ,0
Exp/Cntr=0.3,0.1

Type RM Length L Ch R = 1 ,5098    ,465,465,465
BEGIN DESCRIPTION:
Bruins Creek 11.0
END DESCRIPTION:
XS GIS Cut Line= 4
      1986413.93     13885191.69        1986825.       13885225.
      1988528.84     13885862.71      1988851.19      13886002.4
#Sta/Elev= 30
    4592 1472.49    4668 1470.15  4809.5 1468.54  4833.6 1469.48  4857.7 1465.54
  4893.8 1463.38  4908.8 1457.84  4923.9 1455.31  4938.9 1455.68    4963 1442.12
  4989.5 1439.17    4990 1438.67  5008.8 1439.17  5014.8 1450.76  5030.8 1457.07
  5046.8  1459.8  5124.1 1458.72  5472.9 1462.39  5611.3 1460.39  6328.1  1460.6
  6373.5 1458.81  6619.2 1458.26  6885.9 1462.38  7027.3 1470.33  7044.4 1476.36
    7057 1483.33  7103.3 1489.92  7116.1 1493.51  7143.7 1505.01    7175 1522.38
#Mann= 3 ,-1 , 0
    4592    .035       0  4989.5     .05       0  5008.8    .035       0
#Block Obstruct= 2 , 0
                         5475.34         1463.15
Bank Sta=4989.5,5008.8
XS Rating Curve= 0 ,0
Exp/Cntr=0.3,0.1

Type RM Length L Ch R = 1 ,4633    ,543,543,543
BEGIN DESCRIPTION:
Bruins Creek 10.0
END DESCRIPTION:
XS GIS Cut Line= 3
      1986366.55     13885686.43        1986775.       13885675.
       1988594.1     13885994.78
#Sta/Elev= 30
  4591.4 1464.92  4630.6 1461.76  4690.6 1460.11  4849.7 1458.05  4936.7 1458.36
  4957.7 1453.59    4963  1451.6  4966.7 1449.34    4969 1435.45  4969.5 1434.95
  4988.4 1435.45  4990.8 1436.49  4999.7 1436.63  5002.8 1437.82  5008.9 1446.32
  5011.9 1447.27  5024.1  1449.9  5038.9 1454.77  5063.7 1458.22  5103.3 1455.42
  5121.6 1455.55  5127.7  1454.9  5234.3 1457.64  5795.4 1458.04    6276 1456.41
  6308.3 1458.02  6449.6 1457.41  6639.2  1459.1  6783.5 1463.68    6847 1467.32
#Mann= 3 ,-1 , 0
  4591.4    .035       0    4969     .05       0  4988.4    .035       0
#XS Ineff= 2 , 0
         4937.22 1462.86 5503.36         1463.28
Permanent Ineff=
       F       F
Bank Sta=4969,4988.4
XS Rating Curve= 0 ,0
Exp/Cntr=0.3,0.1

Type RM Length L Ch R = 1 ,4090    ,374,374,374
BEGIN DESCRIPTION:
Bruins Creek 9.0
END DESCRIPTION:
XS GIS Cut Line= 3
      1986275.03     13886075.01      1986763.78     13886198.96
      1988152.53     13886259.69
#Sta/Elev= 30
  4434.1 1481.91  4479.2 1477.68  4513.2 1470.81  4534.9 1469.46  4578.2 1463.52
  4615.4 1460.08  4684.3 1458.12  4717.5 1454.68    4746  1453.3  4828.9 1453.48
  4887.7 1455.05  4921.3  1451.7  4955.3 1446.01  4970.3  1445.6  4979.3 1443.21
  4997.3 1434.17  5008.6 1432.76  5009.1 1432.26    5028 1432.76  5029.9 1437.49
  5036.4 1440.26  5042.4 1445.45    5048 1453.02  5053.7 1455.92  5084.4 1454.98
  6093.4 1453.48  6246.5 1455.17  6285.5 1457.48  6291.6 1456.45  6328.4  1457.1
#Mann= 3 ,-1 , 0
  4434.1    .035       0  5008.6     .05       0    5028    .035       0
#XS Ineff= 2 , 0
                         5061.44         1456.23
Permanent Ineff=
       F       F
Bank Sta=5008.6,5028
XS Rating Curve= 0 ,0
Exp/Cntr=0.3,0.1

Type RM Length L Ch R = 1 ,3716    ,376,376,376
BEGIN DESCRIPTION:
Bruins Creek 8.0
END DESCRIPTION:
XS GIS Cut Line= 3
       1986176.8     13886115.18        1986675.       13886525.
       1987806.2     13886896.04
#Sta/Elev= 30
  4358.9 1483.39  4456.3 1480.04  4503.2 1471.67  4562.9 1465.33  4655.3 1458.92
  4871.9    1451  4880.6 1449.45  4900.1  1439.3  4907.8 1442.75  4915.6 1443.53
  4933.7 1438.73  4961.4 1437.03  4981.6 1430.78  4982.1 1430.28    5001 1430.78
  5001.1 1433.71  5023.1 1447.32  5042.1 1453.05  5052.1  1453.7  5235.2 1452.36
  5345.7 1454.47  5402.6 1452.25  5591.3 1450.84  5858.6 1445.37  5869.8 1446.34
    5892 1451.75  5988.3 1455.01  6040.6 1460.24  6090.6 1468.29  6194.5 1474.09
#Mann= 3 ,-1 , 0
  4358.9    .035       0  4981.6     .05       0    5001    .035       0
#XS Ineff= 2 , 0
                         5063.94         1453.59
Permanent Ineff=
       F       F
#Block Obstruct= 2 , 0
                         5448.55         1451.68
Bank Sta=4981.6,5001
XS Rating Curve= 0 ,0
Exp/Cntr=0.3,0.1

Type RM Length L Ch R = 1 ,3340    ,438,438,438
BEGIN DESCRIPTION:
Bruins Creek 7.0
END DESCRIPTION:
XS GIS Cut Line= 4
      1986274.99     13886374.98      1986376.64     13886722.44
      1986674.97     13886930.36      1987738.52     13886897.88
#Sta/Elev= 30
  4637.1  1479.6  4670.8 1478.85  4681.5 1476.41    4713  1464.8  4746.8  1458.4
  4802.4  1453.6    4874  1451.5  4964.7 1443.15  4977.2 1440.54  4992.8 1430.86
  5010.2 1428.53  5010.7 1428.03  5029.6 1428.53  5030.5 1432.95  5037.2 1434.26
  5052.3 1444.04  5096.7 1451.23  5585.6 1450.93  5665.9 1451.36  5693.7 1452.69
  5712.5 1451.34  5861.1 1450.62  6008.6 1447.79  6131.9 1444.48  6159.5  1444.8
  6221.9 1448.35  6274.7  1448.9  6313.9 1452.53    6375 1467.44  6426.8 1471.95
#Mann= 8 ,-1 , 0
  4637.1    .035       0  5010.2     .05       0  5029.6    .035       0
  5712.5     .07       0  5861.1    .045       0  6008.6    .035       0
  6159.5     .07       0  6274.7      .1       0
#XS Ineff= 2 , 0
                         5695.07         1460.79
Permanent Ineff=
       F       F
#Block Obstruct= 2 , 0
                         5710.79         1451.26
Bank Sta=5010.2,5029.6
XS Rating Curve= 0 ,0
Exp/Cntr=0.3,0.1