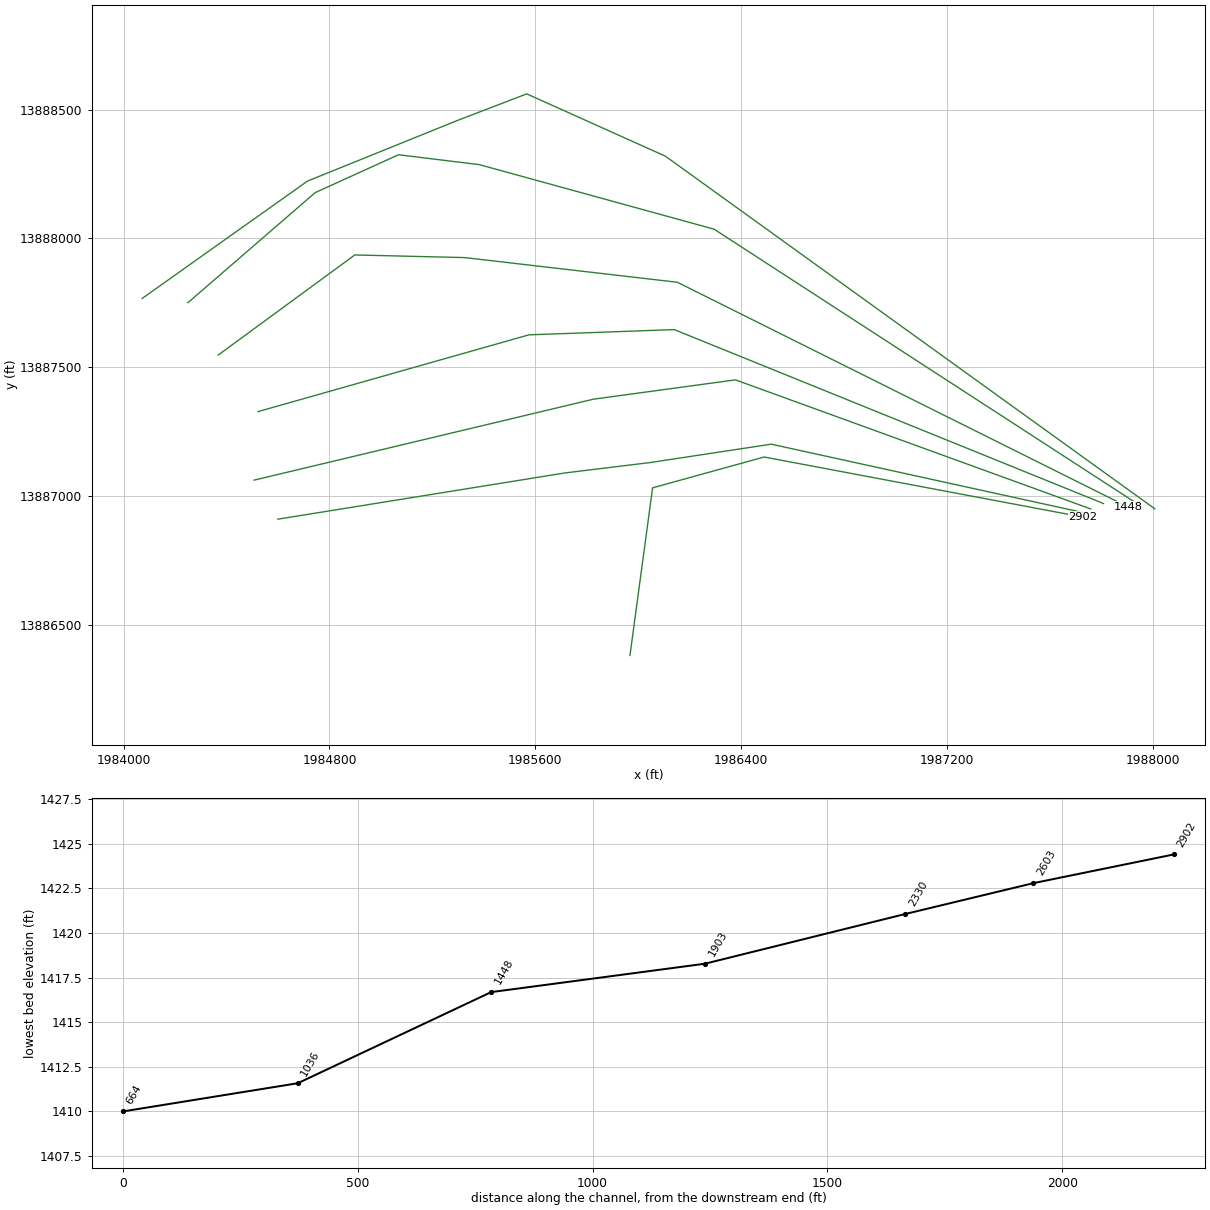
HEC-RAS study Bruins Creek.prj: Bruins Creek Base Level Engineering

--- Bruins Creek.g01 (geometry) --- (continued)

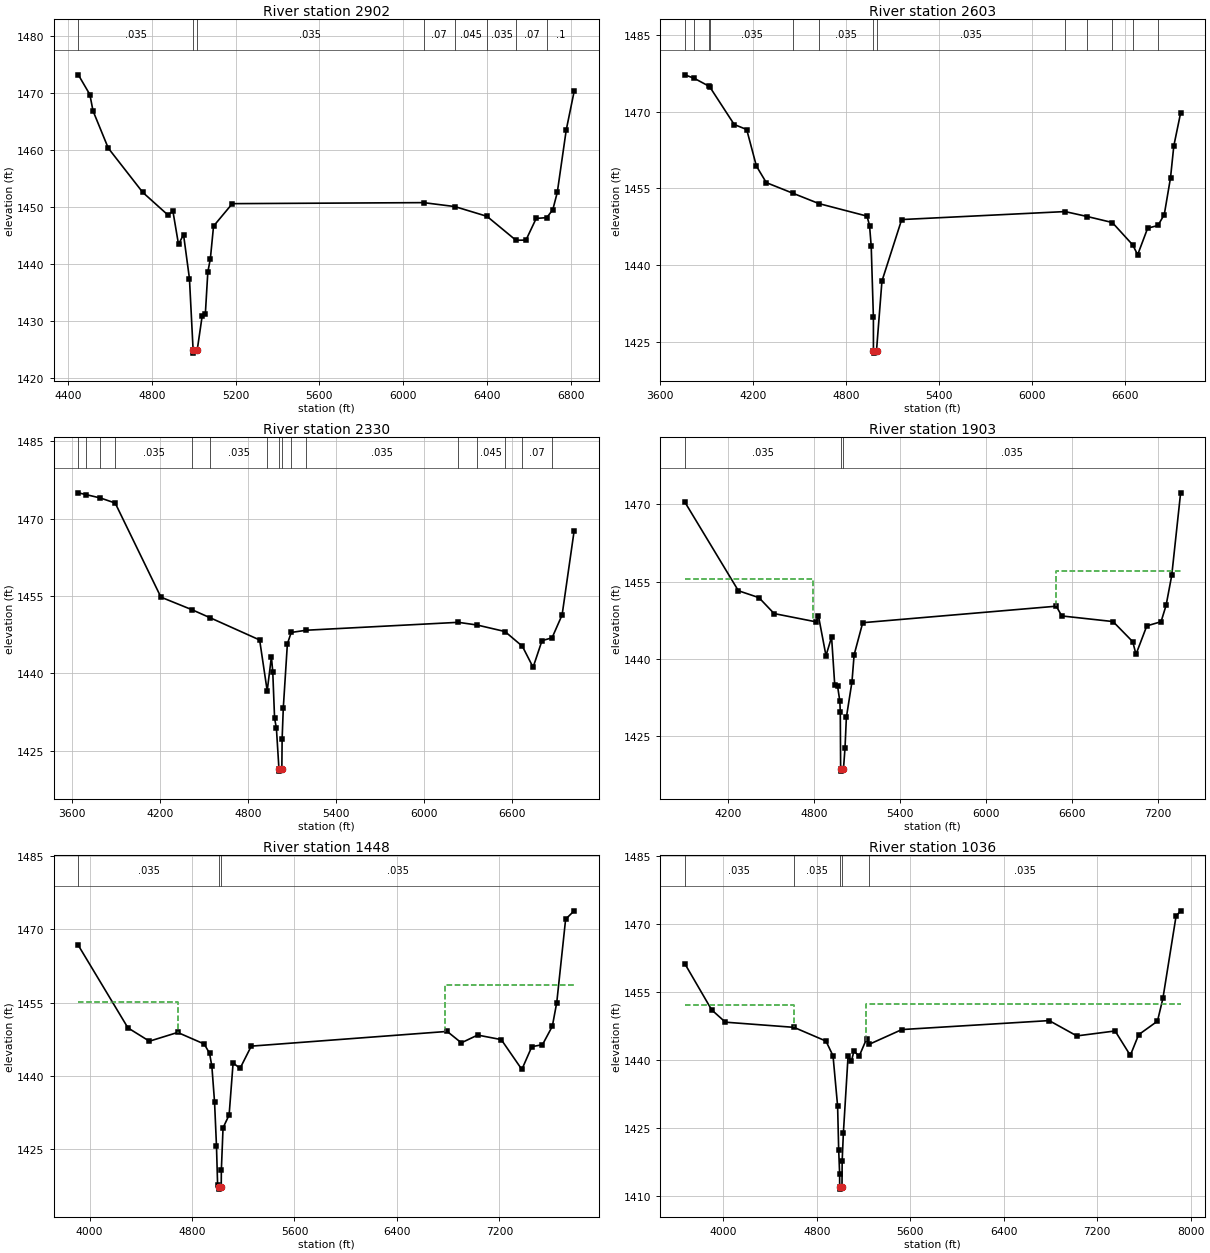
Type RM Length L Ch R = 1 ,2902    ,299,299,299
BEGIN DESCRIPTION:
Bruins Creek 6.0
END DESCRIPTION:
XS GIS Cut Line= 4
      1985967.38     13886379.88      1986055.33     13887030.82
      1986488.57     13887150.51      1987726.79     13886917.43
#Sta/Elev= 30
  4449.6 1473.21  4504.6 1469.75  4519.7 1466.89  4592.4 1460.36    4757  1452.6
  4876.9 1448.64    4901  1449.3  4927.7 1443.48  4951.7 1445.19  4979.9 1437.48
  4997.4 1424.91  4997.9 1424.41  5016.8 1424.91  5040.4 1430.87  5055.7 1431.24
  5067.6 1438.64  5079.7 1440.96  5094.9 1446.68  5184.4 1450.62  6097.1  1450.8
  6246.2 1450.11  6399.8  1448.4  6538.1  1444.2  6585.9 1444.23  6634.7 1448.03
  6685.2 1448.17  6714.1 1449.57  6735.4  1452.6  6778.2 1463.56  6815.9 1470.32
#Mann= 8 ,-1 , 0
  4449.6    .035       0  4997.4     .05       0  5016.8    .035       0
  6097.1     .07       0  6246.2    .045       0  6399.8    .035       0
  6538.1     .07       0  6685.2      .1       0
#Block Obstruct= 2 , 0
                         6094.91         1450.54
Bank Sta=4997.4,5016.8
XS Rating Curve= 0 ,0
Exp/Cntr=0.3,0.1

Type RM Length L Ch R = 1 ,2603    ,273,273,273
BEGIN DESCRIPTION:
Mapping XS dadcaaf1
END DESCRIPTION:
XS GIS Cut Line= 5
       1984599.6     13886909.11      1985714.39      13887088.6
      1986047.06     13887129.17      1986516.25     13887200.39
      1987747.57     13886930.52
#Sta/Elev= 30
  3759.7  1477.2    3820 1476.53    3919 1474.92  3919.4 1474.91  4078.5 1467.49
  4159.1 1466.51  4221.7 1459.37  4285.5 1456.13    4460 1454.02  4625.1 1452.03
  4935.5 1449.58  4951.8 1447.74  4962.6 1443.66  4976.7 1429.77  4976.9  1423.3
  4977.4  1422.8  4996.8  1423.3  5031.8 1436.88  5159.2 1448.91  6213.4 1450.47
    6357  1449.5  6518.2 1448.33  6650.4 1443.94  6681.8 1442.02  6746.3 1447.22
  6812.7 1447.75  6853.6 1449.89  6893.9 1457.09  6915.2 1463.32  6959.1 1469.75
#Mann= 13 ,-1 , 0
  3759.7     .07       0    3820    .035       0    3919     .07       0
  3919.4    .035       0    4460     .07       0  4625.1    .035       0
  4976.9     .05       0  4996.8    .035       0  6213.4     .07       0
    6357    .045       0  6518.2    .035       0  6650.4     .07       0
  6812.7      .1       0
#Block Obstruct= 2 , 0
                         6199.55         1451.18
Bank Sta=4976.9,4996.8
XS Rating Curve= 0 ,0
Exp/Cntr=0.3,0.1

Type RM Length L Ch R = 1 ,2330    ,427,427,427
BEGIN DESCRIPTION:
Bruins Creek 5.0
END DESCRIPTION:
XS GIS Cut Line= 5
        1984507.     13887060.68      1985209.83     13887228.29
        1985825.       13887375.      1986377.15     13887450.12
      1987757.85     13886948.79
#Sta/Elev= 30
  3644.6 1474.99  3694.7 1474.66  3795.3 1473.99  3895.9 1473.01  4207.7 1454.78
  4420.5 1452.33  4545.4 1450.76    4881 1446.48  4932.5 1436.62  4961.2  1443.2
  4970.5 1440.28  4982.8 1431.31  4995.2 1429.41  5012.5 1421.57    5013 1421.07
  5032.4 1421.57  5034.3 1427.31  5042.3 1433.33  5070.1 1445.72  5096.3 1447.94
  5200.1 1448.37  6235.5  1449.9  6363.9 1449.38  6553.7 1448.12  6672.3 1445.27
  6745.8 1441.19  6806.4 1446.35    6875  1446.9  6943.6 1451.34  7025.7 1467.65
#Mann= 16 ,-1 , 0
  3644.6     .07       0  3694.7    .035       0  3795.3     .07       0
  3895.9    .035       0  4420.5     .07       0  4545.4    .035       0
  4932.5    .035       0  5012.5     .05       0  5032.4    .035       0
  5096.3     .07       0  5200.1    .035       0  6235.5     .07       0
  6363.9    .045       0  6553.7    .035       0  6672.3     .07       0
    6875      .1       0
#Block Obstruct= 2 , 0
                         6508.99          1448.5
Bank Sta=5012.5,5032.4
XS Rating Curve= 0 ,0
Exp/Cntr=0.3,0.1

Type RM Length L Ch R = 1 ,1903    ,455,455,455
BEGIN DESCRIPTION:
Bruins Creek 4.0
END DESCRIPTION:
XS GIS Cut Line= 5
       1984522.2     13887326.77      1985127.94     13887498.36
        1985575.       13887625.      1986139.54     13887645.27
      1987807.21      13886969.8
#Sta/Elev= 30
  3900.8 1470.48  4274.5 1453.27  4417.9 1451.93  4523.7 1448.84    4817 1447.23
  4832.6 1448.45  4885.6 1440.68  4924.6 1444.28  4946.5 1435.04  4966.7 1434.71
  4982.3 1431.82  4985.3 1429.73  4987.8 1418.78  4988.3 1418.28  5007.7 1418.78
  5018.3 1422.77  5027.8  1428.7  5066.8  1435.6  5081.8 1440.83  5141.8 1447.07
    6492 1450.27  6530.1 1448.38  6887.7 1447.29  7025.3 1443.38  7047.9 1440.93
  7123.3 1446.45  7222.7 1447.26  7257.8 1450.43  7297.2 1456.24  7359.2 1472.26
#Mann= 3 ,-1 , 0
  3900.8    .035       0  4987.8     .05       0  5007.7    .035       0
#XS Ineff= 2 , 0
         4795.96 1455.56 6486.55         1457.03
Permanent Ineff=
       F       F
#Block Obstruct= 2 , 0
                            6497         1448.98
Bank Sta=4987.8,5007.7
XS Rating Curve= 0 ,0
Exp/Cntr=0.3,0.1

Type RM Length L Ch R = 1 ,1448    ,412,412,412
BEGIN DESCRIPTION:
Bruins Creek 3.0
END DESCRIPTION:
XS GIS Cut Line= 5
      1984368.01     13887546.67      1984898.43     13887935.21
        1985325.       13887925.      1986151.54     13887829.15
      1987902.32     13886956.66
#Sta/Elev= 30
  3911.8 1466.74  4299.2  1449.8  4466.8 1447.06  4687.6 1448.86  4894.7 1446.49
  4936.7 1444.58  4954.7  1441.9  4975.6 1434.62  4990.7 1425.57  4999.7 1417.46
  5007.9 1417.19  5008.4 1416.69  5027.8 1417.19  5028.8 1420.62    5042 1429.27
  5089.5 1431.92  5120.5  1442.6  5174.9 1441.48  5262.5 1446.05  6792.5 1449.07
  6903.1 1446.73  7030.5 1448.32  7214.8 1447.39  7375.7 1441.26  7453.6 1445.94
  7536.6 1446.34  7613.7 1450.13  7648.3    1455  7717.6 1472.11  7784.2 1473.83
#Mann= 3 ,-1 , 0
  3911.8    .035       0  5007.9     .05       0  5027.8    .035       0
#XS Ineff= 2 , 0
         4692.83  1455.2 6778.03         1458.69
Permanent Ineff=
       F       F
#Block Obstruct= 2 , 0
                         6789.24         1448.95
Bank Sta=5007.9,5027.8
XS Rating Curve= 0 ,0
Exp/Cntr=0.3,0.1

Type RM Length L Ch R = 1 ,1036    ,372,372,372
BEGIN DESCRIPTION:
Bruins Creek 2.0
END DESCRIPTION:
XS GIS Cut Line= 6
      1984250.01      13887749.8      1984744.26     13888177.13
      1985068.23     13888324.35      1985382.21     13888285.96
       1986294.4     13888035.25      1987949.11     13886962.08
#Sta/Elev= 30
  3670.8 1461.33  3900.7 1451.14  4018.1 1448.42  4604.9 1447.28    4879 1444.25
  4939.4    1441  4978.7 1429.91  4987.8 1420.32  4996.2 1414.85  4996.3 1412.08
  4996.8 1411.58  5016.2 1412.08  5017.7 1417.79    5028 1423.92  5068.4 1440.99
  5096.4 1439.75  5118.2 1442.04  5163.2 1440.91  5227.1 1444.76  5245.8  1443.5
  5528.9 1446.79  6789.4 1448.77  7026.2 1445.39  7353.8 1446.48  7484.1 1441.09
  7555.4 1445.66  7716.3 1448.64  7762.8 1453.65  7875.5 1471.81  7914.6 1472.99
#Mann= 5 ,-1 , 0
  3670.8    .035       0  4604.9    .035       0  4996.3     .05       0
  5016.2    .035       0  5245.8    .035       0
#XS Ineff= 2 , 0
         4603.14 1452.26 5219.73         1452.44
Permanent Ineff=
       F       F
#Block Obstruct= 2 , 0
                         6794.84         1448.95
Bank Sta=4996.3,5016.2
XS Rating Curve= 0 ,0
Exp/Cntr=0.3,0.1

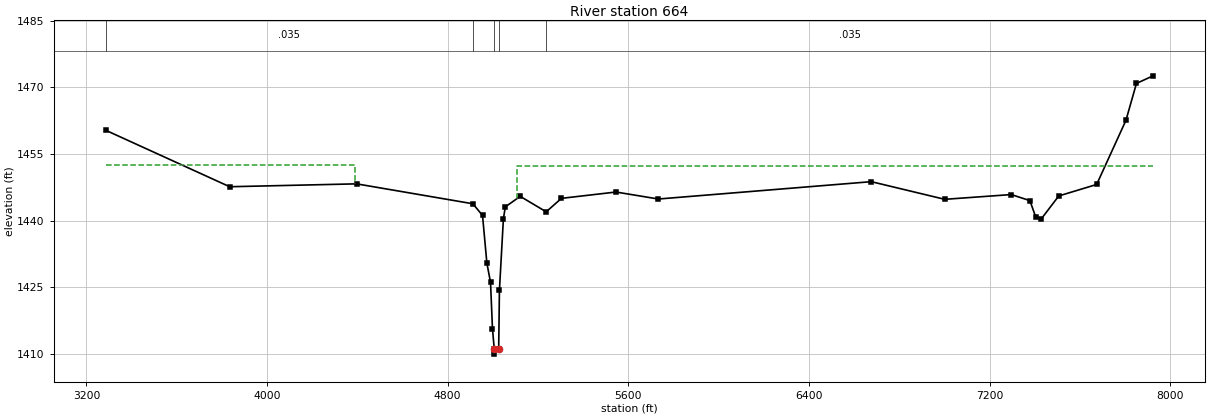
Type RM Length L Ch R = 1 ,664     ,0,0,0
BEGIN DESCRIPTION:
Bruins Creek 1.0
END DESCRIPTION:
XS GIS Cut Line= 6
       1984072.3     13887766.36      1984714.58     13888222.06
      1985295.59      13888456.9      1985566.42     13888560.75
        1986105.     13888318.83      1988006.38     13886949.35
#Sta/Elev= 30
  3286.3 1460.32  3834.6 1447.64  4396.5 1448.29  4911.7 1443.81  4954.4 1441.18
  4973.7 1430.45  4989.8 1426.16  4998.4 1415.75  5006.1 1411.26  5006.2    1410
    5026 1411.26  5029.2 1424.31  5046.9 1440.48  5055.5 1443.12  5121.3 1445.48
  5236.4    1442  5303.9 1445.03  5545.6 1446.45  5733.4 1444.88  6676.2 1448.78
  7001.6 1444.81  7296.2 1445.88  7378.7 1444.52  7404.6 1440.82  7429.7 1440.45
  7506.7 1445.57  7674.4 1448.15  7804.1 1462.57  7850.6 1470.87  7924.2 1472.58
#Mann= 5 ,-1 , 0
  3286.3    .035       0  4911.7    .035       0  5006.1     .05       0
    5026    .035       0  5236.4    .035       0
#XS Ineff= 2 , 0
         4390.13 1452.44 5107.62         1452.26
Permanent Ineff=
       F       F
#Block Obstruct= 2 , 0
                         6677.13         1448.58
Bank Sta=5006.1,5026
XS Rating Curve= 0 ,0
Exp/Cntr=0.3,0.1

Chan Stop Cuts=-1
Use User Specified Reach Order=0
Composite Channel Slope=5