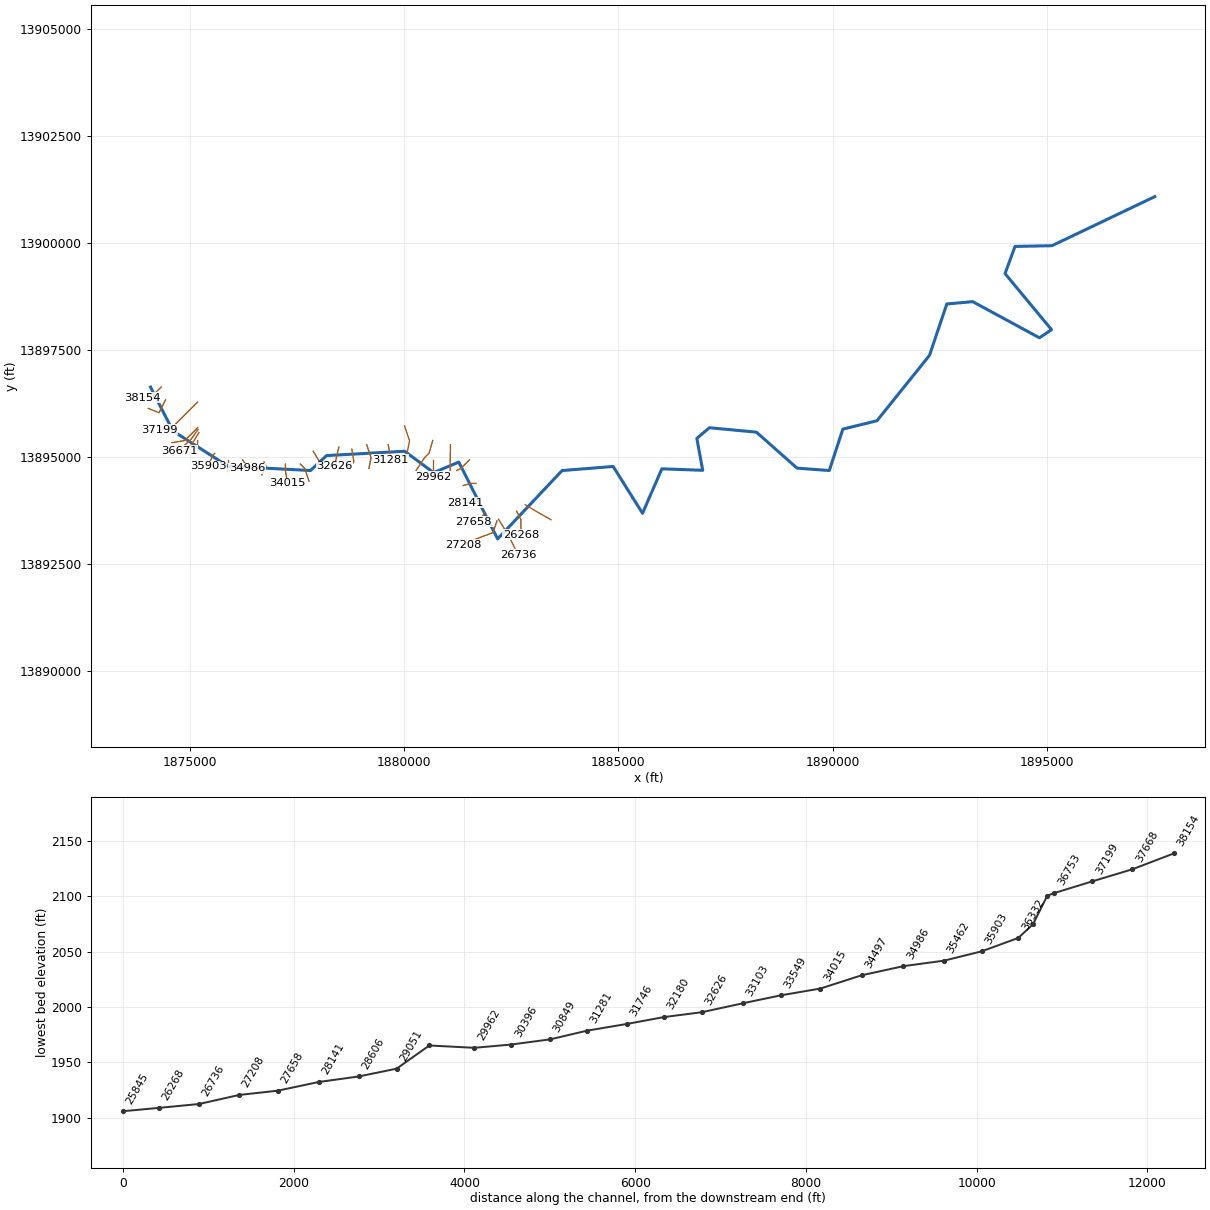
--- Bushwhack Creek.prj (project) ---

Proj Title=Bushwhack Creek Base Level Engineering
Current Plan=p01
Default Exp/Contr=0.3,0.1
English Units
Geom File=g01
Flow File=f01
Plan File=p01
Y Axis Title=Elevation
X Axis Title(PF)=Main Channel Distance
X Axis Title(XS)=Station
BEGIN DESCRIPTION:
Bushwhack Creek
END DESCRIPTION:
DSS Export Rating Curves= 0
DSS Export Rating Curve Sorted= 0
DSS Export Volume Flow Curves= 0
DXF OffsetX= 0
DXF OffsetY= 0
DXF ScaleX= 1
DXF ScaleY= 10

--- Bushwhack Creek.p01 (plan) ---

Plan Title=Multiple Run
Short Identifier=Multiple
Geom File=g01
Flow File=f01
Subcritical Flow
K Sum by GR= 0
Std Step Tol= 0.01
Critical Tol= 0.01
Num of Std Step Trials= 20
Max Error Tol= 0.3
Flow Tol Ratio= 0.001
Split Flow NTrial= 30
Split Flow Tol= 0.02
Split Flow Ratio= 0.02
Log Output Level= 0
Friction Slope Method= 1
Unsteady Friction Slope Method= 2
Unsteady Bridges Friction Slope Method= 1
Parabolic Critical Depth
Global Vel Dist=  1 , 1 , 1
Global Log Level= 0
CheckData=True
Encroach Param= -1, 0, 0, 0
BEGIN DESCRIPTION:
Multiple Run
END DESCRIPTION:

--- Bushwhack Creek.f01 (steady flow) ---

Flow Title=Multiple
Program Version=4.10
Number of Profiles= 7
Profile Names=10-year,25-year,50-year,1pct_min,100-year,1pct_plu,500-year
River Rch & RM=Bushwhack Creek,Reach-1         ,38154
     205     312     402     253     506    1009     783
River Rch & RM=Bushwhack Creek,Reach-1         ,37668
    1078    1848    2585    1752    3496    6975    6307
River Rch & RM=Bushwhack Creek,Reach-1         ,33549
    1458    2532    3573    2437    4863    9703    8900
River Rch & RM=Bushwhack Creek,Reach-1         ,28606
    2149    3814    5460    3774    7529   15023   14151
River Rch & RM=Bushwhack Creek,Reach-1         ,26736
    2971    5328    7683    5341   10657   21264   20267
River Rch & RM=Bushwhack Creek,Reach-1         ,22094
    3254    5851    8451    5883   11738   23420   22384
River Rch & RM=Bushwhack Creek,Reach-1         ,19757
    3455    6227    9007    6277   12524   24990   23940
River Rch & RM=Bushwhack Creek,Reach-1         ,18110
    4529    8245   12008    8417   16793   33507   32476
River Rch & RM=Bushwhack Creek,Reach-1         ,14004
    4708    8579   12503    8767   17493   34903   33861
River Rch & RM=Bushwhack Creek,Reach-1         ,12212
    5535   10144   14838   10438   20827   41556   40577
River Rch & RM=Bushwhack Creek,Reach-1         ,9444
    5883   10797   15809   11129   22206   44306   43325
River Rch & RM=Bushwhack Creek,Reach-1         ,6455
    5759   10583   15505   10919   21787   43470   42562
River Rch & RM=Bushwhack Creek,Reach-1         ,3502
    5873   10785   15792   11114   22176   44246   43263
Boundary for River Rch & Prof#=Bushwhack Creek,Reach-1         , 1
Up Type= 0
Dn Type= 3
Dn Slope=0.008
Boundary for River Rch & Prof#=Bushwhack Creek,Reach-1         , 2
Up Type= 0
Dn Type= 3
Dn Slope=0.008
Boundary for River Rch & Prof#=Bushwhack Creek,Reach-1         , 3
Up Type= 0
Dn Type= 3
Dn Slope=0.008
Boundary for River Rch & Prof#=Bushwhack Creek,Reach-1         , 4
Up Type= 0
Dn Type= 3
Dn Slope=0.008
Boundary for River Rch & Prof#=Bushwhack Creek,Reach-1         , 5
Up Type= 0
Dn Type= 3
Dn Slope=0.008
Boundary for River Rch & Prof#=Bushwhack Creek,Reach-1         , 6
Up Type= 0
Dn Type= 3
Dn Slope=0.008
Boundary for River Rch & Prof#=Bushwhack Creek,Reach-1         , 7
Up Type= 0
Dn Type= 3
Dn Slope=0.008
DSS Import GetInterval= 0
DSS Import GetPeak= 0
DSS Import FillOption= 0

--- Bushwhack Creek.g01 (geometry) ---

Geom Title=Existing Conditions
Program Version=4.10

River Reach=Bushwhack Creek ,Reach-1
Reach XY= 30
        1874075.       13896625.      1874597.86     13895601.16
      1875880.93     13894777.24      1877809.66     13894674.95
      1878185.43     13895023.95      1880009.94     13895125.71
      1880685.67     13894625.74      1881273.78     13894871.57
      1882180.88     13893076.96      1883685.33     13894674.13
      1884877.74     13894769.67      1885564.38      13893675.6
        1886015.     13894714.37      1886969.56     13894680.18
      1886832.49     13895424.97        1887125.       13895675.
      1888223.54     13895571.46      1889172.58     13894730.54
        1889925.       13894675.      1890241.49     13895642.05
      1891038.31      13895838.4      1892263.91     13897364.63
      1892668.92     13898566.87       1893273.5     13898621.38
      1894831.13     13897776.78      1895114.84      13897965.3
      1894028.67     13899276.59      1894261.64     13899911.72
      1895123.72     13899928.52        1897525.       13901075.

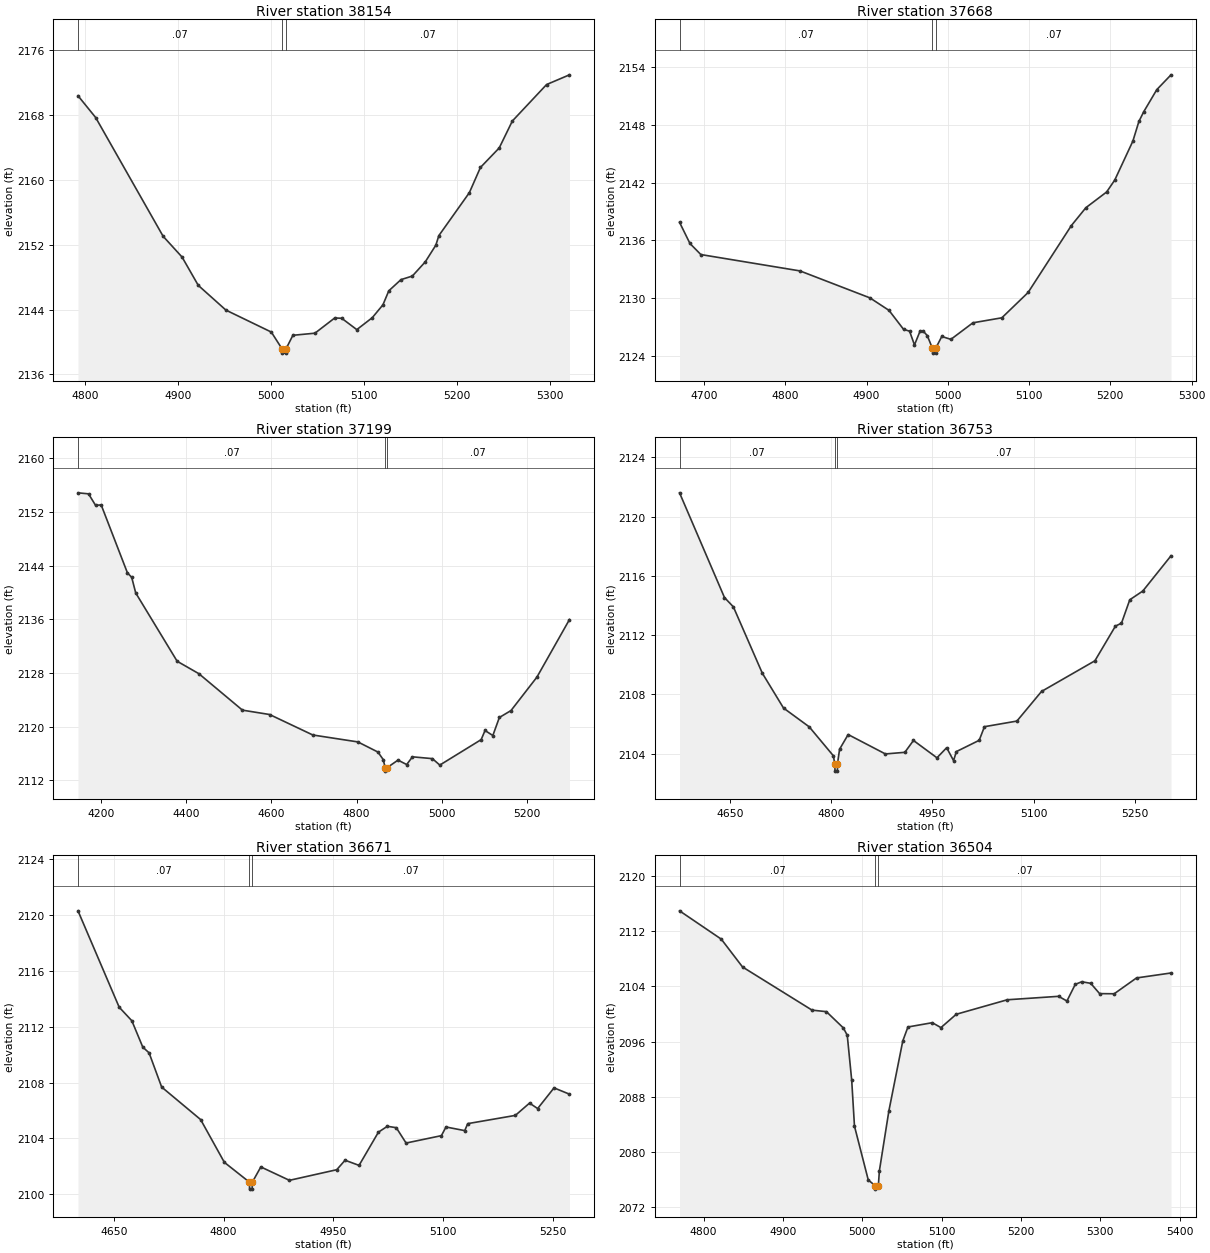
Type RM Length L Ch R = 1 ,38154   ,486,486,486
BEGIN DESCRIPTION:
Bushwhack Creek 79.0
END DESCRIPTION:
XS GIS Cut Line= 3
      1874324.98     13896624.98        1874175.       13896475.
      1873875.03     13896375.01
#Sta/Elev= 30
  4792.7 2170.38  4811.7 2167.69  4884.2 2153.04  4904.6 2150.47    4922 2146.98
  4951.7 2143.93  5000.5 2141.22  5012.2 2139.12  5012.4 2138.62  5015.9 2138.62
  5016.2 2139.12  5023.7 2140.82  5047.4 2141.08  5068.7 2142.96  5076.2 2142.92
  5092.4 2141.52    5109 2142.99  5120.5 2144.58  5126.8 2146.31  5139.9 2147.69
  5152.1 2148.13    5166 2149.88  5177.4 2151.95  5180.6 2153.12  5213.4 2158.42
  5225.3 2161.53  5245.5 2163.94  5259.6 2167.26  5296.4 2171.76    5321 2172.96
#Mann= 3 ,-1 , 0
  4792.7     .07       0  5012.2     .05       0  5016.2     .07       0
Bank Sta=5012.2,5016.2
XS Rating Curve= 0 ,0
Exp/Cntr=0.3,0.1

Type RM Length L Ch R = 1 ,37668   ,469,469,469
BEGIN DESCRIPTION:
Bushwhack Creek 78.0
END DESCRIPTION:
XS GIS Cut Line= 3
      1874424.99     13896324.97        1874275.       13896025.
      1874025.04     13896124.99
#Sta/Elev= 30
    4670 2137.88  4682.8 2135.68  4696.2 2134.53  4818.2 2132.83  4904.2 2130.03
  4927.7 2128.73  4945.6 2126.76    4953 2126.57    4959 2125.14  4965.8 2126.56
  4969.7 2126.58  4974.7 2126.12  4981.1 2124.79  4981.4 2124.29  4984.9 2124.29
  4985.1 2124.79  4992.6 2126.02  5003.8 2125.72  5030.9 2127.44  5066.5 2127.96
  5098.8 2130.59    5152 2137.54  5169.9  2139.4  5195.4 2141.03  5205.4 2142.27
  5227.7 2146.32  5235.1 2148.36    5241 2149.36  5257.1 2151.66  5274.6  2153.2
#Mann= 3 ,-1 , 0
    4670     .07       0  4981.1     .05       0  4985.1     .07       0
Bank Sta=4981.1,4985.1
XS Rating Curve= 0 ,0
Exp/Cntr=0.3,0.1

Type RM Length L Ch R = 1 ,37199   ,446,446,446
BEGIN DESCRIPTION:
Bushwhack Creek 77.0
END DESCRIPTION:
XS GIS Cut Line= 3
      1875175.02     13896275.02        1874575.       13895675.
      1874274.99       13895625.
#Sta/Elev= 30
  4146.7 2154.83  4171.4 2154.68  4187.9 2152.97  4201.1 2153.03  4262.6 2142.92
  4272.7 2142.24  4282.1 2139.92  4379.3 2129.75  4430.2  2127.9  4532.4 2122.47
  4596.1 2121.82  4697.5 2118.77  4803.1 2117.74  4850.2 2116.23  4862.5 2115.12
  4867.3 2113.89  4867.5 2113.39  4871.3 2113.89  4897.3 2115.03  4917.6 2114.37
  4931.2 2115.52  4977.9 2115.25  4995.3 2114.29  5092.3 2118.08  5101.4 2119.44
  5119.7 2118.69    5135 2121.38  5162.3 2122.41  5223.1 2127.39  5299.4 2135.96
#Mann= 3 ,-1 , 0
  4146.7     .07       0  4867.3     .05       0  4871.3     .07       0
Bank Sta=4867.3,4871.3
XS Rating Curve= 0 ,0
Exp/Cntr=0.3,0.1

Type RM Length L Ch R = 1 ,36753   ,82,82,82
BEGIN DESCRIPTION:
Bushwhack Creek 76.0
END DESCRIPTION:
XS GIS Cut Line= 3
      1875175.01     13895675.01        1874875.       13895375.
      1874575.02       13895325.
#Sta/Elev= 30
  4575.4 2121.61    4642 2114.54  4655.2 2113.91  4698.1 2109.43  4729.5 2107.08
  4767.6 2105.81  4803.3 2103.86  4805.5 2103.32  4805.8 2102.82  4809.3 2102.82
  4809.5 2103.32  4812.6  2104.3  4825.3 2105.29  4880.5 2103.98  4909.3 2104.09
  4922.1 2104.89  4956.9 2103.72  4971.3  2104.4  4981.5 2103.53  4985.7 2104.14
  5019.5  2104.9  5027.3 2105.82  5075.4  2106.2  5111.9  2108.2    5191 2110.27
  5221.4 2112.61  5230.4 2112.81  5242.7 2114.39    5262 2114.98  5303.8 2117.36
#Mann= 3 ,-1 , 0
  4575.4     .07       0  4805.5     .05       0  4809.5     .07       0
Bank Sta=4805.5,4809.5
XS Rating Curve= 0 ,0
Exp/Cntr=0.3,0.1

Type RM Length L Ch R = 1 ,36671   ,167,167,167
BEGIN DESCRIPTION:
Bushwhack Creek 76.1
END DESCRIPTION:
XS GIS Cut Line= 3
      1875185.96     13895635.75        1875018.     13895398.79
      1874736.74     13895140.96
#Sta/Elev= 30
  4600.8  2120.3  4657.1  2113.4  4674.4 2112.43  4689.4 2110.54    4698 2110.13
  4715.2 2107.68  4768.5 2105.35  4800.9 2102.29  4835.2 2100.87  4835.4 2100.37
  4838.9 2100.37  4839.2 2100.87  4850.8 2101.96  4889.9    2101  4954.6 2101.76
    4966 2102.44  4985.1 2102.07  5011.6 2104.45  5023.8 2104.87    5036 2104.77
  5049.4 2103.67  5097.7  2104.2    5104 2104.82  5129.6 2104.56  5133.7 2105.06
  5198.8 2105.65  5218.2 2106.53  5229.3 2106.14  5251.7 2107.62  5272.8 2107.17
#Mann= 3 ,-1 , 0
  4600.8     .07       0  4835.2     .05       0  4839.2     .07       0
Bank Sta=4835.2,4839.2
XS Rating Curve= 0 ,0
Exp/Cntr=0.3,0.1

Type RM Length L Ch R = 1 ,36504   ,172,172,172
BEGIN DESCRIPTION:
Mapping XS 6d188fcd
END DESCRIPTION:
XS GIS Cut Line= 3
      1875204.06     13895562.04      1875033.87     13895277.75
      1874803.28     13895104.94
#Sta/Elev= 30
  4769.6 2114.95  4822.2 2110.85    4849 2106.82  4936.6 2100.57  4954.7 2100.35
  4976.1 2097.99    4981 2096.93  4986.6 2090.44  4990.1 2083.77  5007.5 2075.97
  5016.2 2075.15  5016.4 2074.65  5020.2 2075.15  5021.5 2077.31  5033.5    2086
    5051 2096.11  5057.5 2098.13  5088.2 2098.75  5099.1 2098.04  5118.4 2099.97
  5182.7 2102.07  5247.4 2102.57  5257.9 2101.89  5268.4  2104.3  5276.6 2104.68
  5287.9 2104.45  5299.1 2102.96  5317.5 2102.94  5345.6 2105.23  5389.1 2105.95
#Mann= 3 ,-1 , 0
  4769.6     .07       0  5016.2     .05       0  5020.2     .07       0
Bank Sta=5016.2,5020.2
XS Rating Curve= 0 ,0
Exp/Cntr=0.3,0.1

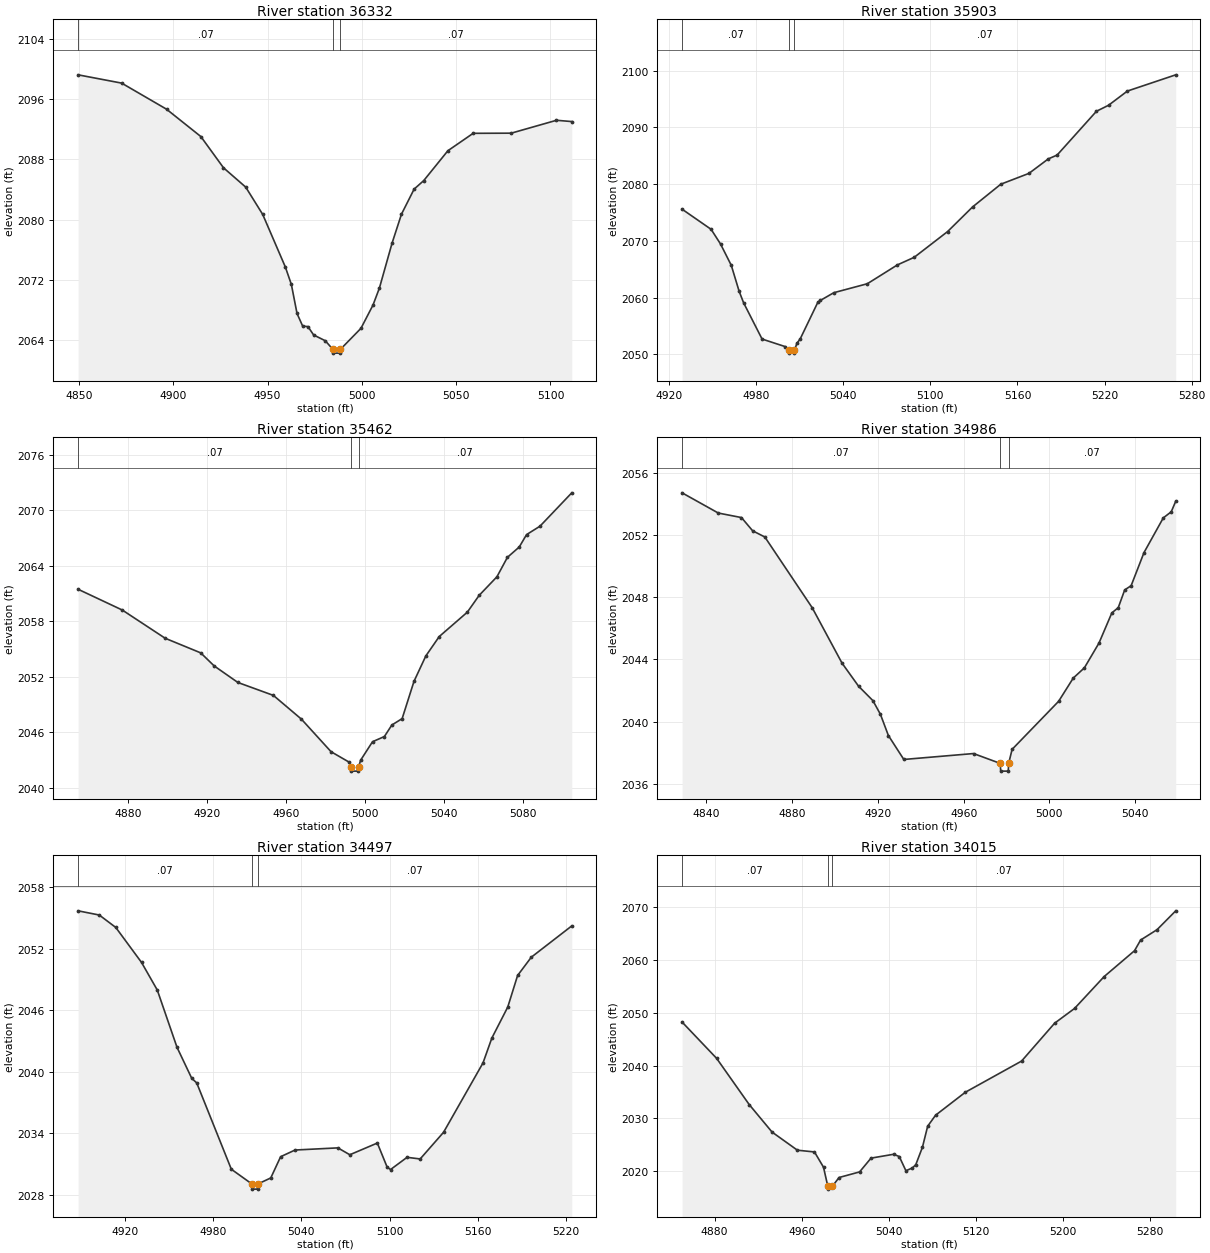
Type RM Length L Ch R = 1 ,36332   ,429,429,429
BEGIN DESCRIPTION:
Bushwhack Creek 75.0
END DESCRIPTION:
XS GIS Cut Line= 3
        1875175.     13895375.02        1875175.       13895225.
      1875075.02     13895175.01
#Sta/Elev= 30
  4849.5 2099.22  4872.6 2098.12  4896.4 2094.66  4914.6 2091.03  4926.6 2086.89
  4938.4 2084.32  4947.4  2080.7  4959.4 2073.73  4962.6 2071.41  4965.6 2067.56
  4968.6 2065.88  4971.4 2065.82  4974.4 2064.71  4980.6 2063.94  4984.6  2062.8
  4984.9  2062.3  4988.4  2062.3  4988.6  2062.8  4999.5 2065.59  5005.9 2068.68
  5009.3 2070.94    5016 2076.89    5021 2080.74  5027.7 2084.06  5032.8 2085.19
  5045.6 2089.15    5059 2091.46  5079.2 2091.48  5103.2 2093.19  5111.3 2093.02
#Mann= 3 ,-1 , 0
  4849.5     .07       0  4984.6     .05       0  4988.6     .07       0
Bank Sta=4984.6,4988.6
XS Rating Curve= 0 ,0
Exp/Cntr=0.3,0.1

Type RM Length L Ch R = 1 ,35903   ,441,441,441
BEGIN DESCRIPTION:
Bushwhack Creek 74.0
END DESCRIPTION:
XS GIS Cut Line= 3
      1875575.03     13895075.03        1875525.       13895025.
        1875425.     13894775.01
#Sta/Elev= 30
    4929 2075.57    4949 2072.02  4955.5 2069.43  4962.9 2065.67  4968.3  2061.1
  4971.4 2059.06  4984.1 2052.68  4999.9 2051.36  5002.4  2050.7  5002.7  2050.2
  5006.2  2050.2  5006.4  2050.7  5008.1 2051.93  5010.4 2052.73  5022.5 2059.16
  5024.2 2059.48  5033.5 2060.85  5056.6 2062.43  5077.3 2065.75  5088.9 2067.09
  5111.9 2071.63  5129.1 2075.97  5148.5 2079.97  5167.9 2081.88  5181.2 2084.43
  5187.3 2085.11  5214.4 2092.83  5222.7 2093.88  5235.7 2096.39    5269 2099.25
#Mann= 3 ,-1 , 0
    4929     .07       0  5002.4     .05       0  5006.4     .07       0
Bank Sta=5002.4,5006.4
XS Rating Curve= 0 ,0
Exp/Cntr=0.3,0.1

Type RM Length L Ch R = 1 ,35462   ,476,476,476
BEGIN DESCRIPTION:
Bushwhack Creek 73.0
END DESCRIPTION:
XS GIS Cut Line= 3
        1875875.     13894925.03        1875875.       13894775.
        1875875.     13894675.03
#Sta/Elev= 30
  4854.5 2061.46  4876.9 2059.21  4898.6 2056.16  4916.6 2054.58  4923.4 2053.17
  4935.4 2051.38  4953.4 2049.98  4967.6 2047.41  4982.6 2043.89  4991.6 2042.78
  4992.6 2042.29  4992.9 2041.79  4996.4 2041.79  4996.6 2042.29  4997.6 2042.98
  5003.6 2044.97  5009.6 2045.53  5013.4 2046.78  5018.6 2047.47  5024.6  2051.5
  5030.6 2054.25  5037.4 2056.35  5051.6 2058.98  5057.6  2060.8  5066.6 2062.81
  5071.9 2064.91  5077.9 2066.03  5081.6 2067.37  5088.4 2068.28  5104.5 2071.89
#Mann= 3 ,-1 , 0
  4854.5     .07       0  4992.6     .05       0  4996.6     .07       0
Bank Sta=4992.6,4996.6
XS Rating Curve= 0 ,0
Exp/Cntr=0.3,0.1

Type RM Length L Ch R = 1 ,34986   ,489,489,489
BEGIN DESCRIPTION:
Bushwhack Creek 72.0
END DESCRIPTION:
XS GIS Cut Line= 3
      1876225.02     13894924.97        1876325.       13894775.
        1876325.     13894725.04
#Sta/Elev= 30
  4828.7  2054.7  4845.6  2053.4  4856.4 2053.11  4861.6 2052.26  4867.3 2051.86
  4889.4 2047.31  4903.3 2043.75    4911 2042.27  4917.7 2041.34  4921.2 2040.46
  4924.9  2039.1  4932.1 2037.56  4964.6 2037.94    4977 2037.31  4977.3 2036.81
  4980.8 2036.81    4981 2037.31  4982.6 2038.21  5004.3  2041.3  5011.1 2042.79
  5016.3 2043.45  5023.1 2045.04  5029.1 2046.98  5032.1 2047.32  5035.1 2048.46
  5038.1 2048.73  5044.1 2050.86  5053.1 2053.09  5056.8 2053.48  5058.9 2054.16
#Mann= 3 ,-1 , 0
  4828.7     .07       0    4977     .05       0    4981     .07       0
Bank Sta=4977,4981
XS Rating Curve= 0 ,0
Exp/Cntr=0.3,0.1

Type RM Length L Ch R = 1 ,34497   ,482,482,482
BEGIN DESCRIPTION:
Bushwhack Creek 71.0
END DESCRIPTION:
XS GIS Cut Line= 3
      1876725.01     13894874.97        1876775.       13894775.
      1876674.99     13894574.98
#Sta/Elev= 30
  4888.4 2055.69  4902.8 2055.28    4914 2054.07  4931.5 2050.66  4942.2 2047.97
  4955.6 2042.39  4965.6 2039.37    4969 2038.92  4992.5 2030.51  5006.5 2029.07
  5006.8 2028.57  5010.3 2028.57  5010.5 2029.07  5019.3 2029.66    5026 2031.73
  5035.8 2032.38  5064.9 2032.59    5073 2031.92  5091.7 2033.06  5098.4  2030.7
  5100.7 2030.48  5111.9 2031.67  5120.8 2031.51  5136.7 2034.11  5163.5 2040.87
  5169.5 2043.29  5180.3 2046.31    5187 2049.39  5196.3 2051.17  5223.8 2054.22
#Mann= 3 ,-1 , 0
  4888.4     .07       0  5006.5     .05       0  5010.5     .07       0
Bank Sta=5006.5,5010.5
XS Rating Curve= 0 ,0
Exp/Cntr=0.3,0.1

Type RM Length L Ch R = 1 ,34015   ,466,466,466
BEGIN DESCRIPTION:
Bushwhack Creek 70.0
END DESCRIPTION:
XS GIS Cut Line= 3
        1877225.       13894825.        1877225.       13894675.
      1877274.99     13894375.03
#Sta/Elev= 30
    4850 2048.26  4881.8 2041.38  4911.8 2032.62  4932.8 2027.42  4956.1 2023.99
  4971.8 2023.66  4980.1 2020.77  4984.1 2017.12  4984.4 2016.62  4988.1 2017.12
  4994.4 2018.82  5013.3 2019.88  5023.8 2022.49  5044.6 2023.22  5049.8 2022.79
  5055.9  2020.1  5061.9 2020.64    5065 2021.26  5071.1 2024.55  5075.9 2028.53
  5083.2 2030.62  5110.6 2034.97  5162.3 2040.87  5192.7 2048.04    5211 2050.83
  5238.3 2056.88  5266.2 2061.77  5271.8 2063.79  5286.9 2065.75  5304.1 2069.32
#Mann= 3 ,-1 , 0
    4850     .07       0  4984.1     .05       0  4988.1     .07       0
Bank Sta=4984.1,4988.1
XS Rating Curve= 0 ,0
Exp/Cntr=0.3,0.1

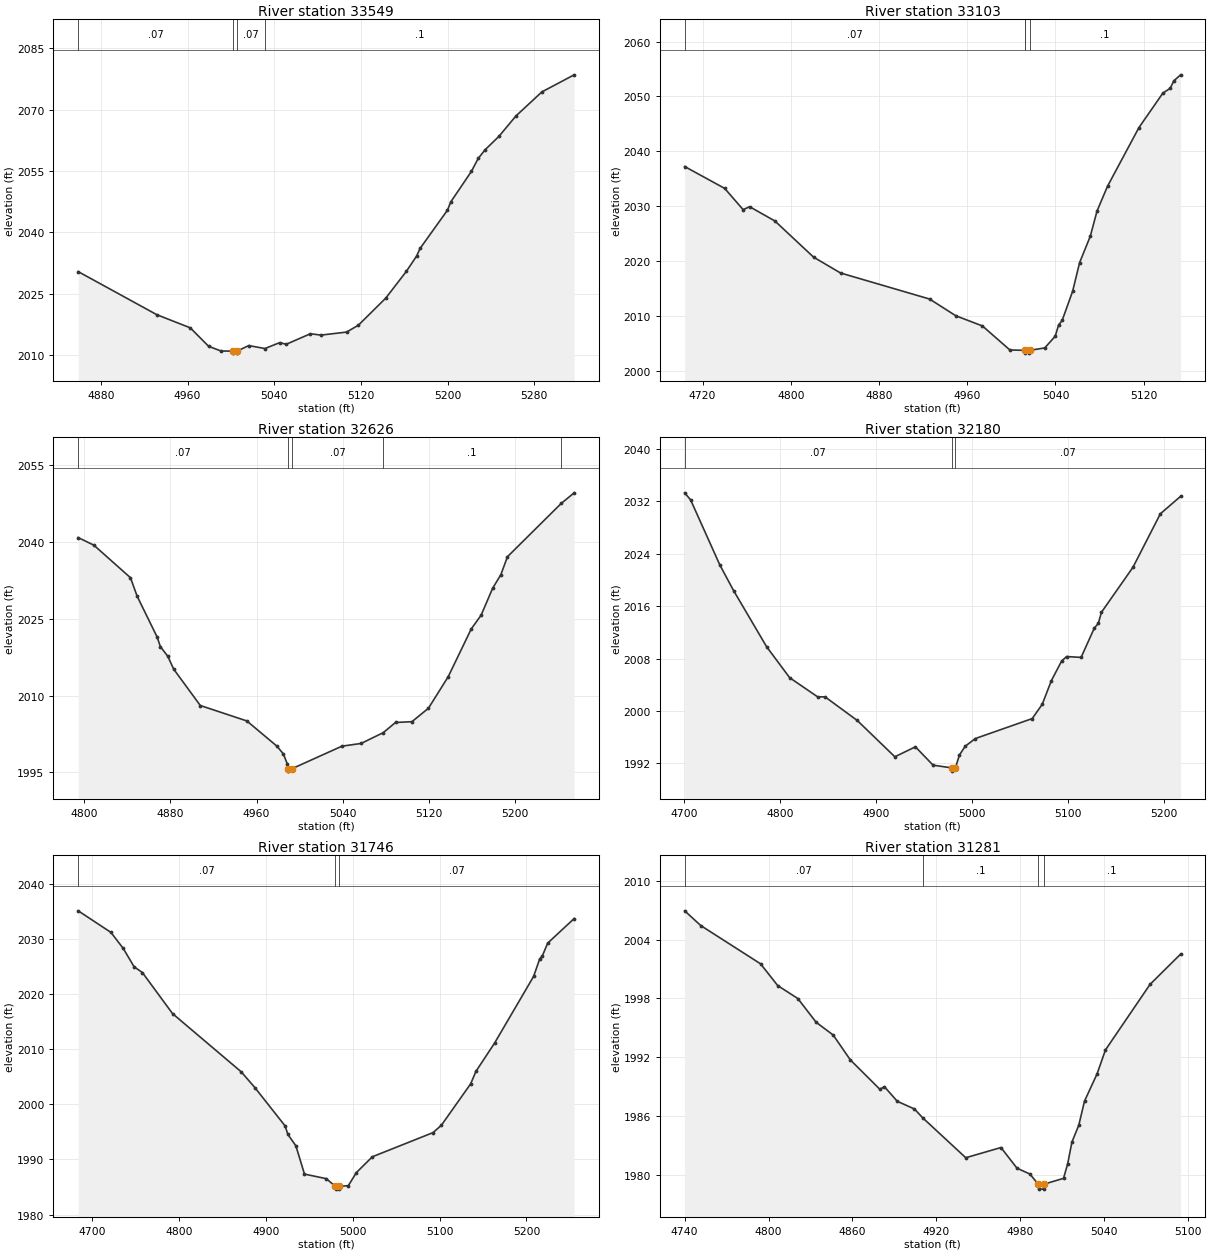
Type RM Length L Ch R = 1 ,33549   ,446,446,446
BEGIN DESCRIPTION:
Bushwhack Creek 69.0
END DESCRIPTION:
XS GIS Cut Line= 3
      1877574.99     13894825.01        1877675.       13894725.
      1877775.01     13894424.96
#Sta/Elev= 30
  4859.1 2030.39  4931.6 2019.86  4962.5 2016.64  4979.5 2012.11    4991 2010.96
  5001.8 2010.95  5002.1 2010.45  5005.6 2010.45  5005.8 2010.95  5016.5  2012.3
  5031.4 2011.57  5044.9    2013  5051.2 2012.63  5073.4 2015.19  5083.1 2014.86
  5106.8  2015.6  5117.7 2017.29    5143 2023.93  5161.9 2030.44  5171.4  2034.2
  5174.6 2036.06  5199.9 2045.44    5203 2047.47    5222 2054.93  5228.3  2058.1
  5234.7 2060.23  5247.3 2063.46  5263.1 2068.48    5287 2074.36  5316.8 2078.54
#Mann= 4 ,-1 , 0
  4859.1     .07       0  5001.8     .05       0  5005.8     .07       0
  5031.4      .1       0
Bank Sta=5001.8,5005.8
XS Rating Curve= 0 ,0
Exp/Cntr=0.3,0.1

Type RM Length L Ch R = 1 ,33103   ,477,477,477
BEGIN DESCRIPTION:
Bushwhack Creek 68.0
END DESCRIPTION:
XS GIS Cut Line= 3
      1877874.98     13895125.03        1878025.       13894875.
        1878075.     13894724.99
#Sta/Elev= 30
  4703.8 2037.24  4740.1 2033.25  4756.8 2029.38  4762.7 2029.92  4785.6 2027.32
  4820.7 2020.73  4845.1 2017.85  4925.9  2013.1  4949.7 2010.05  4973.8  2008.2
  4998.7 2003.82  5012.2 2003.76  5012.5 2003.75  5012.7 2003.25  5016.2 2003.25
  5016.5 2003.75  5030.3  2004.2  5039.8 2006.33  5042.9  2008.4  5046.1 2009.21
  5055.6 2014.53  5061.9 2019.73  5071.6 2024.54  5077.7 2029.13  5087.2 2033.64
  5115.7 2044.33  5137.4 2050.61  5144.1  2051.5  5147.3 2052.84  5153.5 2053.94
#Mann= 4 ,-1 , 0
  4703.8     .07       0  5012.2      .1       0  5012.5     .05       0
  5016.5      .1       0
Bank Sta=5012.5,5016.5
XS Rating Curve= 0 ,0
Exp/Cntr=0.3,0.1

Type RM Length L Ch R = 1 ,32626   ,446,446,446
BEGIN DESCRIPTION:
Bushwhack Creek 67.0
END DESCRIPTION:
XS GIS Cut Line= 3
      1878475.01     13895225.04        1878425.       13895025.
      1878375.01     13894775.05
#Sta/Elev= 30
  4794.2  2040.9  4808.8 2039.41  4842.8 2033.05    4849 2029.43  4867.5 2021.49
  4870.6 2019.58  4877.4 2017.72    4883 2015.17  4907.7 2008.07    4951 2005.05
  4978.9 2000.13    4985 1998.59  4988.7 1996.58  4989.2 1995.74  4989.4 1995.24
  4993.2 1995.74  5039.4 2000.12  5057.2 2000.65  5077.8 2002.76  5089.2 2004.75
  5104.5 2004.91  5119.8 2007.53  5138.2  2013.7  5159.6 2023.03  5168.8 2025.73
  5179.6 2031.03  5187.1 2033.62  5193.3 2037.16  5243.3 2047.58  5255.3 2049.65
#Mann= 5 ,-1 , 0
  4794.2     .07       0  4989.2     .05       0  4993.2     .07       0
  5077.8      .1       0  5243.3     .07       0
Bank Sta=4989.2,4993.2
XS Rating Curve= 0 ,0
Exp/Cntr=0.3,0.1

Type RM Length L Ch R = 1 ,32180   ,434,434,434
BEGIN DESCRIPTION:
Bushwhack Creek 66.0
END DESCRIPTION:
XS GIS Cut Line= 3
        1878775.     13895175.01        1878825.       13894875.
      1878674.99     13894724.99
#Sta/Elev= 30
  4700.8  2033.3    4707 2032.22  4737.4 2022.29  4751.7 2018.38  4786.1 2009.81
  4810.1 2005.08  4839.3 2002.15  4846.9 2002.16  4880.4 1998.56  4919.6 1993.01
    4941 1994.53  4959.4 1991.73  4978.7 1991.32    4979 1990.82  4982.7 1991.32
  4986.8 1993.27  4992.9 1994.63  5003.5  1995.8  5062.6 1998.84    5073 2001.01
  5082.6 2004.65  5093.2 2007.62  5098.4 2008.31  5113.5 2008.18  5127.2 2012.64
  5131.4 2013.37  5134.7 2015.07  5167.5 2021.94    5196  2030.1  5217.1 2032.77
#Mann= 3 ,-1 , 0
  4700.8     .07       0  4978.7     .05       0  4982.7     .07       0
Bank Sta=4978.7,4982.7
XS Rating Curve= 0 ,0
Exp/Cntr=0.3,0.1

Type RM Length L Ch R = 1 ,31746   ,465,465,465
BEGIN DESCRIPTION:
Bushwhack Creek 65.0
END DESCRIPTION:
XS GIS Cut Line= 3
        1879125.     13895274.99        1879225.       13894975.
      1879174.99     13894724.97
#Sta/Elev= 30
  4683.8 2035.17  4721.5 2031.25  4735.6 2028.35  4748.2    2025  4757.7 2023.96
  4792.5 2016.49  4871.5 2005.93  4887.3 2003.05  4922.1 1996.09  4925.3 1994.54
  4934.5 1992.48  4944.4 1987.34  4969.6 1986.51  4979.9 1985.11  4980.2 1984.61
  4983.7 1984.61  4983.9 1985.11  4994.9 1985.24  5004.2 1987.62  5022.6 1990.49
  5092.5 1994.88  5102.1 1996.22  5135.8 2003.74  5141.9 2006.01  5163.3 2011.13
  5208.3 2023.25  5215.3 2026.43  5218.4 2026.99  5224.5  2029.3    5255 2033.77
#Mann= 3 ,-1 , 0
  4683.8     .07       0  4979.9     .05       0  4983.9     .07       0
Bank Sta=4979.9,4983.9
XS Rating Curve= 0 ,0
Exp/Cntr=0.3,0.1

Type RM Length L Ch R = 1 ,31281   ,432,432,432
BEGIN DESCRIPTION:
Bushwhack Creek 64.0
END DESCRIPTION:
XS GIS Cut Line= 3
        1879625.     13895275.01        1879675.       13895025.
        1879675.     13894924.96
#Sta/Elev= 30
    4740 2006.93  4751.5 2005.43  4794.3 2001.53  4806.6 1999.31    4821 1997.99
  4834.1 1995.57  4846.3 1994.27  4858.6 1991.73  4879.7 1988.74    4883    1989
  4892.2 1987.51  4904.5 1986.73  4910.3 1985.84  4941.2 1981.76  4966.4  1982.8
  4977.9 1980.69  4987.1  1980.1  4993.1 1979.06  4993.4 1978.56  4996.9 1978.56
  4997.1 1979.06  5011.2 1979.66  5014.2 1981.17  5017.2 1983.36  5022.1 1985.07
  5026.2 1987.53  5035.2 1990.31  5041.2 1992.75  5073.1 1999.43    5095 2002.52
#Mann= 4 ,-1 , 0
    4740     .07       0  4910.3      .1       0  4993.1     .05       0
  4997.1      .1       0
Bank Sta=4993.1,4997.1
XS Rating Curve= 0 ,0
Exp/Cntr=0.3,0.1

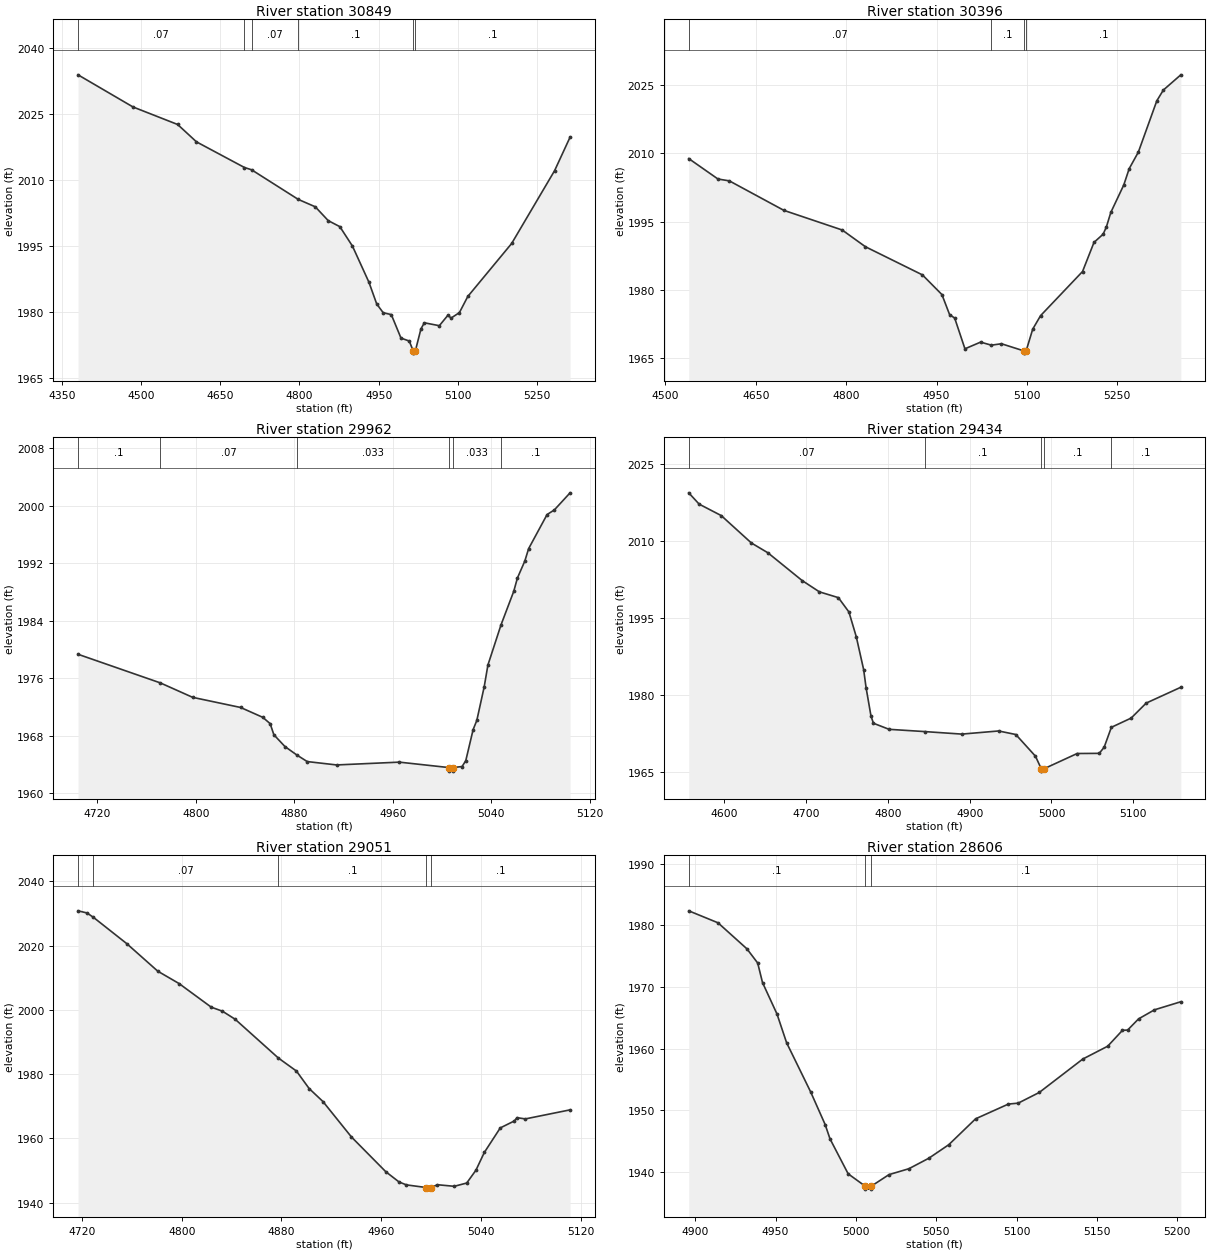
Type RM Length L Ch R = 1 ,30849   ,453,453,453
BEGIN DESCRIPTION:
Bushwhack Creek 63.0
END DESCRIPTION:
XS GIS Cut Line= 4
      1880007.37      13895716.5      1880123.57     13895366.83
        1880075.       13895125.      1879974.99     13894824.96
#Sta/Elev= 30
  4380.8 2033.93  4484.9 2026.63  4569.4 2022.65    4605 2018.71  4695.9 2012.88
  4709.3 2012.37  4797.7 2005.64  4829.9 2003.96  4854.4 2000.82  4876.4 1999.45
  4900.3 1995.03  4931.5 1986.82  4946.2 1981.89  4958.5  1979.9  4973.8 1979.48
  4992.1 1974.15  5007.8 1973.47  5015.3 1971.23  5015.5 1970.73  5019.3 1971.23
  5029.9 1976.23  5036.3 1977.62  5064.7 1976.96    5081 1979.34  5086.9 1978.69
  5102.7 1979.93  5118.6  1983.6  5201.6 1995.63  5282.9 2012.17  5312.2 2019.78
#Mann= 6 ,-1 , 0
  4380.8     .07       0  4695.9      .1       0  4709.3     .07       0
  4797.7      .1       0  5015.3     .05       0  5019.3      .1       0
Bank Sta=5015.3,5019.3
XS Rating Curve= 0 ,0
Exp/Cntr=0.3,0.1

Type RM Length L Ch R = 1 ,30396   ,434,434,434
BEGIN DESCRIPTION:
Bushwhack Creek 62.0
END DESCRIPTION:
XS GIS Cut Line= 4
      1880664.44     13895376.47      1880579.33      13895081.2
        1880475.       13894975.      1880275.01     13894675.02
#Sta/Elev= 30
  4538.6 2008.83  4587.1 2004.34    4606 2003.93  4696.5 1997.45  4793.3 1993.13
  4831.9 1989.45  4926.4 1983.27  4958.8 1978.94  4971.5 1974.55    4980 1973.77
    4997 1967.02    5023 1968.49  5040.9 1967.82  5057.6 1968.13  5094.6 1966.57
  5094.8 1966.07  5098.6 1966.57  5109.5 1971.34  5122.5  1974.3  5192.2 1984.01
  5211.2 1990.41  5226.4 1992.22  5231.8 1993.82  5239.1 1996.99  5260.7 2003.05
  5269.6 2006.61  5284.8 2010.25  5315.5 2021.54  5326.3 2023.89  5355.3 2027.24
#Mann= 4 ,-1 , 0
  4538.6     .07       0  5040.9      .1       0  5094.6     .05       0
  5098.6      .1       0
Bank Sta=5094.6,5098.6
XS Rating Curve= 0 ,0
Exp/Cntr=0.3,0.1

Type RM Length L Ch R = 1 ,29962   ,528,528,528
BEGIN DESCRIPTION:
Bushwhack Creek 61.0
END DESCRIPTION:
XS GIS Cut Line= 3
        1880675.     13894924.99        1880675.       13894625.
        1880675.     13894524.99
#Sta/Elev= 30
  4704.2 1979.35  4771.1 1975.37  4797.4 1973.36  4836.4 1971.95  4854.4 1970.58
  4860.4  1969.7  4863.4 1968.16  4872.4 1966.52  4882.1 1965.34  4890.5 1964.43
  4914.4 1963.96  4965.4 1964.35  5005.4  1963.6  5005.6  1963.1  5009.1  1963.1
  5009.4  1963.6  5016.4 1963.74  5019.4 1964.55  5025.4 1968.88  5028.4 1970.16
  5034.4 1974.84  5037.4 1977.85  5048.1 1983.46  5058.4  1988.1  5061.4 1989.96
  5067.4 1992.31  5070.5 1994.04  5085.5 1998.78  5091.4 1999.42  5104.2  2001.8
#Mann= 6 ,-1 , 0
  4704.2      .1       0  4771.1     .07       0  4882.1    .033       0
  5005.4    .033       0  5009.4    .033       0  5048.1      .1       0
Bank Sta=5005.4,5009.4
XS Rating Curve= 0 ,0
Exp/Cntr=0.3,0.1

Type RM Length L Ch R = 1 ,29434   ,383,383,383
BEGIN DESCRIPTION:
Bushwhack Creek 60.0
END DESCRIPTION:
XS GIS Cut Line= 3
      1881079.14     13895276.47      1881072.63     13894865.02
        1881075.     13894675.04
#Sta/Elev= 30
  4556.6 2019.38  4569.3 2017.18  4596.3 2014.95  4633.2 2009.61  4653.3 2007.71
  4695.2  2002.3  4716.3  2000.1  4739.5 1998.97  4752.4 1996.18  4761.4 1991.35
  4770.4 1984.95  4773.4 1981.41  4779.4 1975.89  4782.4 1974.51  4801.5 1973.33
  4845.1 1972.89  4890.4  1972.4  4935.4 1973.01  4956.4 1972.32  4980.4  1968.1
  4987.4 1965.69  4987.6 1965.19  4991.4 1965.69  5031.4 1968.62  5058.4 1968.65
  5064.4 1969.84  5073.2 1973.72  5097.4 1975.52  5115.8 1978.44  5158.1 1981.52
#Mann= 5 ,-1 , 0
  4556.6     .07       0  4845.1      .1       0  4987.4    .033       0
  4991.4      .1       0  5073.2      .1       0
Bank Sta=4987.4,4991.4
XS Rating Curve= 0 ,0
Exp/Cntr=0.3,0.1

Type RM Length L Ch R = 1 ,29051   ,445,445,445
BEGIN DESCRIPTION:
Bushwhack Creek 59.0
END DESCRIPTION:
XS GIS Cut Line= 3
        1881525.       13894925.        1881325.       13894725.
      1881224.96     13894674.98
#Sta/Elev= 30
  4716.8 2030.85    4724 2030.19  4729.2 2028.81  4755.8 2020.67  4780.8 2012.06
  4797.8 2008.23  4823.7 2000.86  4832.6 1999.62  4842.8 1997.12  4877.5 1985.04
    4892 1980.99  4902.2 1975.54  4913.3 1971.49  4936.1 1960.48  4963.7 1949.65
  4974.3 1946.47  4980.2 1945.56  4996.1 1944.74  4996.4 1944.24  5000.1 1944.74
  5005.1 1945.61  5018.6 1945.12  5028.6 1946.14    5036 1950.14  5042.7 1955.65
  5055.5 1963.29  5066.9 1965.48  5068.9 1966.48  5075.6 1966.09  5111.5 1968.91
#Mann= 5 ,-1 , 0
  4716.8      .1       0  4729.2     .07       0  4877.5      .1       0
  4996.1     .05       0  5000.1      .1       0
Bank Sta=4996.1,5000.1
XS Rating Curve= 0 ,0
Exp/Cntr=0.3,0.1

Type RM Length L Ch R = 1 ,28606   ,465,465,465
BEGIN DESCRIPTION:
Bushwhack Creek 58.0
END DESCRIPTION:
XS GIS Cut Line= 3
        1881675.       13894375.        1881575.       13894375.
      1881374.96     13894324.99
#Sta/Elev= 30
    4896 1982.33  4914.2 1980.39  4932.2 1976.17  4938.9 1973.87  4941.9  1970.7
  4950.9 1965.61  4956.9 1960.94  4971.9 1952.95  4980.9 1947.67  4983.9 1945.36
  4995.2 1939.69  5005.7 1937.71  5005.9 1937.21  5009.4 1937.21  5009.7 1937.71
  5020.6 1939.56    5033 1940.52  5045.4 1942.22  5057.8 1944.41  5074.5 1948.61
  5094.9    1951    5101 1951.15  5114.1 1952.88  5141.2  1958.3  5156.7 1960.38
  5165.9 1962.96  5169.1    1963  5175.9 1964.81  5185.8 1966.28  5202.2 1967.59
#Mann= 3 ,-1 , 0
    4896      .1       0  5005.7     .05       0  5009.7      .1       0
Bank Sta=5005.7,5009.7
XS Rating Curve= 0 ,0
Exp/Cntr=0.3,0.1

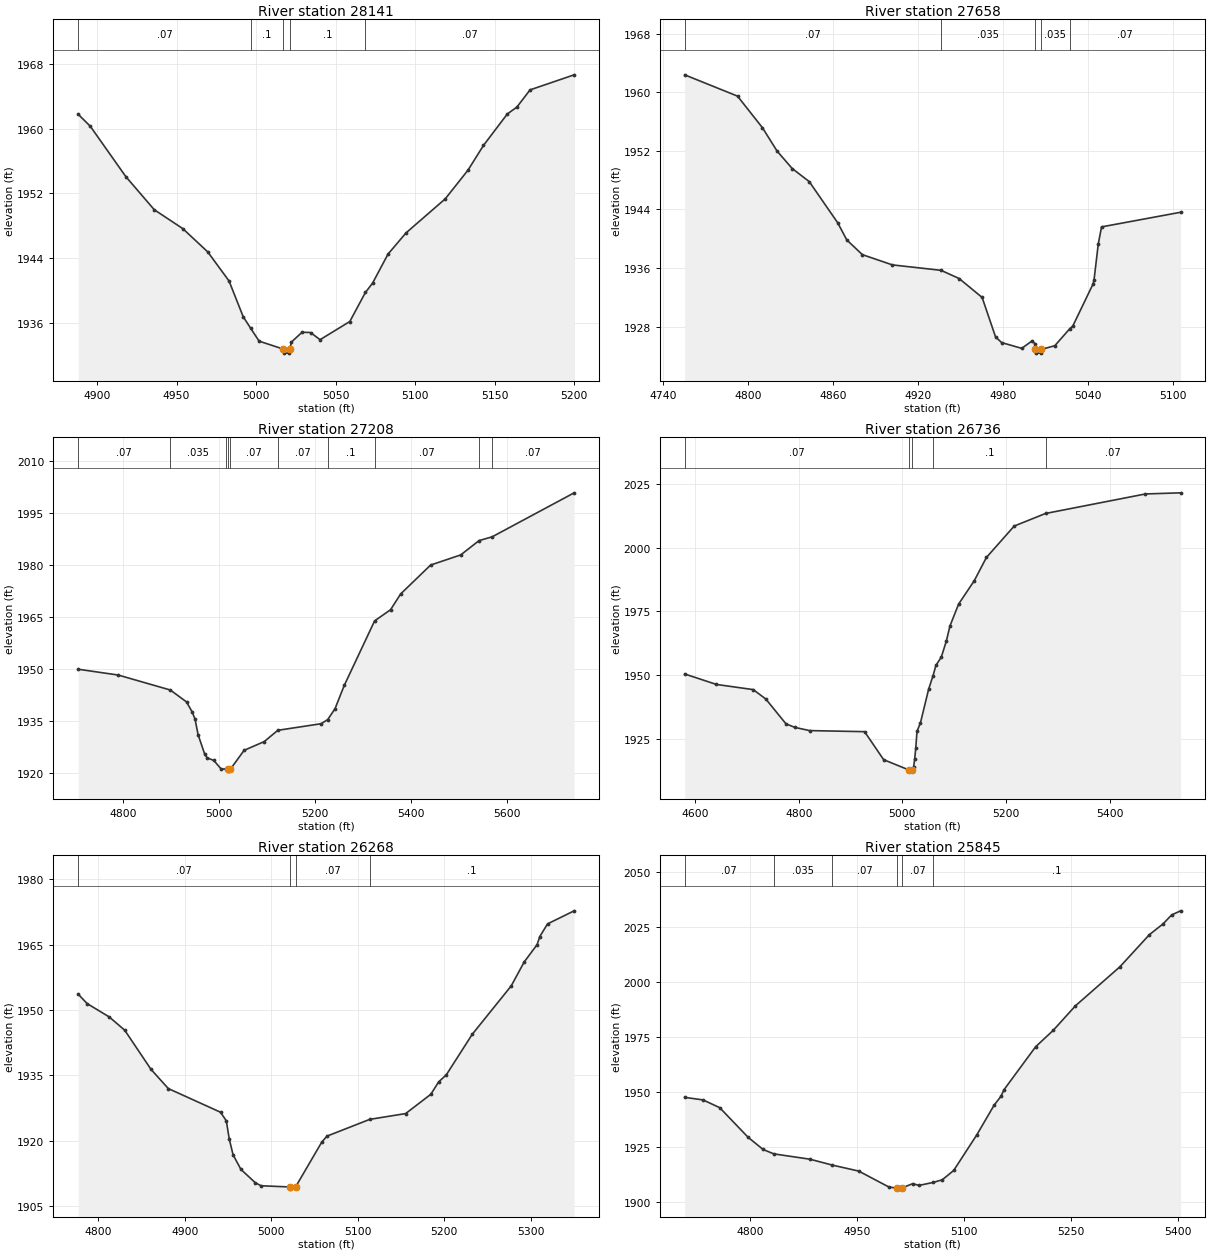
Type RM Length L Ch R = 1 ,28141   ,483,483,483
BEGIN DESCRIPTION:
Bushwhack Creek 57.0
END DESCRIPTION:
XS GIS Cut Line= 3
      1881725.01       13893975.        1881625.       13893925.
      1881425.11       13893925.
#Sta/Elev= 30
  4888.2 1961.78  4895.8  1960.3  4918.1 1954.08    4936 1949.98  4953.9 1947.65
  4969.6 1944.77    4983 1941.17  4991.9 1936.75  4996.6 1935.32  5001.9 1933.73
  5017.1 1932.75  5017.4 1932.25  5020.9 1932.25  5021.2 1932.75  5022.2 1933.62
  5028.9 1934.83  5034.2  1934.8  5040.2 1933.91  5058.9 1936.16  5068.7 1939.75
  5073.2  1940.9  5082.9 1944.49  5094.2 1947.11  5118.9 1951.33  5133.2 1954.88
  5142.9 1957.93  5157.9 1961.82  5163.9 1962.67  5172.2  1964.8  5199.9 1966.66
#Mann= 5 ,-1 , 0
  4888.2     .07       0  4996.6      .1       0  5017.1     .05       0
  5021.2      .1       0  5068.7     .07       0
Bank Sta=5017.1,5021.2
XS Rating Curve= 0 ,0
Exp/Cntr=0.3,0.1

Type RM Length L Ch R = 1 ,27658   ,450,450,450
BEGIN DESCRIPTION:
Bushwhack Creek 56.0
END DESCRIPTION:
XS GIS Cut Line= 3
      1881875.02     13893675.03        1881725.       13893475.
      1881625.04       13893475.
#Sta/Elev= 30
  4755.2 1962.38  4792.5 1959.47  4810.1 1955.15  4820.4 1951.97  4831.1 1949.58
  4843.1  1947.8  4863.2 1942.17  4869.6 1939.83  4880.6 1937.82  4901.8 1936.42
  4936.1 1935.68  4948.9 1934.56  4965.1 1931.98  4974.6 1926.58  4978.9 1925.81
  4993.1 1925.02  5000.4 1926.05  5002.5 1925.63  5002.6 1924.87  5002.8 1924.37
  5006.4 1924.37  5006.7 1924.87  5016.4 1925.38    5027 1927.71  5029.1 1928.07
  5043.4 1933.81  5044.1 1934.38  5047.1 1939.29  5049.4 1941.61  5105.2 1943.61
#Mann= 5 ,-1 , 0
  4755.2     .07       0  4936.1    .035       0  5002.6    .035       0
  5006.7    .035       0    5027     .07       0
Bank Sta=5002.6,5006.7
XS Rating Curve= 0 ,0
Exp/Cntr=0.3,0.1

Type RM Length L Ch R = 1 ,27208   ,472,472,472
BEGIN DESCRIPTION:
Bushwhack Creek 55.0
END DESCRIPTION:
XS GIS Cut Line= 4
      1882166.67      13893499.7        1882075.       13893225.
        1881675.       13893075.      1881387.46     13892942.49
#Sta/Elev= 30
  4706.1 1949.96  4789.5 1948.28    4898 1943.96  4931.8 1940.52  4943.7 1937.58
  4949.6 1935.52  4955.9 1931.05  4969.7 1925.43  4974.9 1924.36  4988.7 1923.61
  5004.1 1921.12  5014.3 1921.18  5017.5 1921.03  5017.9 1920.53  5022.9 1921.03
  5051.8 1926.54  5093.7 1929.06    5122 1932.32  5212.5 1934.23    5226 1935.42
  5241.2 1938.55  5260.5  1945.3  5323.7 1963.92    5357 1967.16    5378 1971.71
  5440.4 1980.05  5503.2 1982.98  5541.3 1987.11  5568.6  1988.2  5739.5 2000.91
#Mann= 10 ,-1 , 0
  4706.1     .07       0    4898    .035       0  5014.3     .07       0
  5017.5    .035       0  5022.9     .07       0    5122     .07       0
    5226      .1       0  5323.7     .07       0  5541.3      .1       0
  5568.6     .07       0
Bank Sta=5017.5,5022.9
XS Rating Curve= 0 ,0
Exp/Cntr=0.3,0.1

Type RM Length L Ch R = 1 ,26736   ,468,468,468
BEGIN DESCRIPTION:
Bushwhack Creek 54.0
END DESCRIPTION:
XS GIS Cut Line= 3
      1882201.16     13893536.79        1882425.       13893175.
      1882661.26     13892699.27
#Sta/Elev= 30
    4580 1950.43  4641.2 1946.33  4712.2  1944.3  4736.5 1940.61  4775.3  1930.9
  4792.7 1929.47  4821.1 1928.23    4927 1927.81  4963.8 1916.82    5012 1912.84
  5012.5 1912.34  5018.8 1912.84  5021.4 1913.84  5023.6 1916.94  5025.8  1921.5
  5028.1 1927.94  5034.8  1931.3  5050.6 1944.49  5059.1 1949.77  5064.6 1953.79
    5075 1957.04  5084.8  1963.4  5091.7 1969.25  5108.4 1977.84  5138.6    1987
    5162 1996.11  5215.6 2008.42    5276 2013.35  5468.8 2021.01  5536.6 2021.45
#Mann= 5 ,-1 , 0
    4580     .07       0    5012     .05       0  5018.8     .07       0
  5059.1      .1       0    5276     .07       0
Bank Sta=5012,5018.8
XS Rating Curve= 0 ,0
Exp/Cntr=0.3,0.1

Type RM Length L Ch R = 1 ,26268   ,423,423,423
BEGIN DESCRIPTION:
Bushwhack Creek 53.0
END DESCRIPTION:
XS GIS Cut Line= 3
      1882625.02     13893724.96        1882725.       13893525.
        1882725.     13893174.97
#Sta/Elev= 30
  4776.7 1953.61    4787 1951.46  4812.7 1948.37  4830.5 1945.34  4860.8 1936.38
  4880.9 1931.95  4941.3 1926.52    4948 1924.54  4951.4 1920.37  4955.8 1916.75
  4964.9  1913.4  4981.6 1910.32  4988.3 1909.64  5021.2 1909.37  5021.7 1908.87
  5028.1 1909.37  5058.5  1919.7  5064.5 1921.04  5113.9 1924.88  5155.4 1926.21
  5184.5 1930.63  5193.5 1933.46  5202.5 1935.12  5232.5 1944.42  5277.5 1955.51
  5292.5    1961  5307.5    1965  5310.5 1966.81  5319.5 1969.74  5350.3 1972.74
#Mann= 4 ,-1 , 0
  4776.7     .07       0  5021.2     .05       0  5028.1     .07       0
  5113.9      .1       0
Bank Sta=5021.2,5028.1
XS Rating Curve= 0 ,0
Exp/Cntr=0.3,0.1

Type RM Length L Ch R = 1 ,25845   ,471,471,471
BEGIN DESCRIPTION:
Bushwhack Creek 52.0
END DESCRIPTION:
XS GIS Cut Line= 3
      1882824.97     13893875.02        1883075.       13893725.
        1883425.       13893525.
#Sta/Elev= 30
  4708.4 1947.59  4734.2 1946.41  4757.5 1942.89  4797.2 1929.43  4818.2 1923.89
  4833.1 1921.88  4883.9 1919.44  4915.4 1916.75  4952.1 1914.05  4994.7 1906.75
  5005.5 1906.33    5006 1905.83  5012.5 1906.33  5027.7  1908.3  5036.8 1907.53
  5056.5 1908.88  5069.2 1910.07  5085.2 1914.31  5117.6 1930.52  5141.8    1944
  5151.7 1948.18  5155.6 1951.01    5200  1970.6  5224.7 1978.09  5255.8 1989.24
    5318 2006.97  5359.4 2021.62  5378.5 2026.51  5390.5 2030.58  5403.1 2032.45
#Mann= 6 ,-1 , 0
  4708.4     .07       0  4833.1    .035       0  4915.4     .07       0
  5005.5     .05       0  5012.5     .07       0  5056.5      .1       0
Bank Sta=5005.5,5012.5
XS Rating Curve= 0 ,0
Exp/Cntr=0.3,0.1