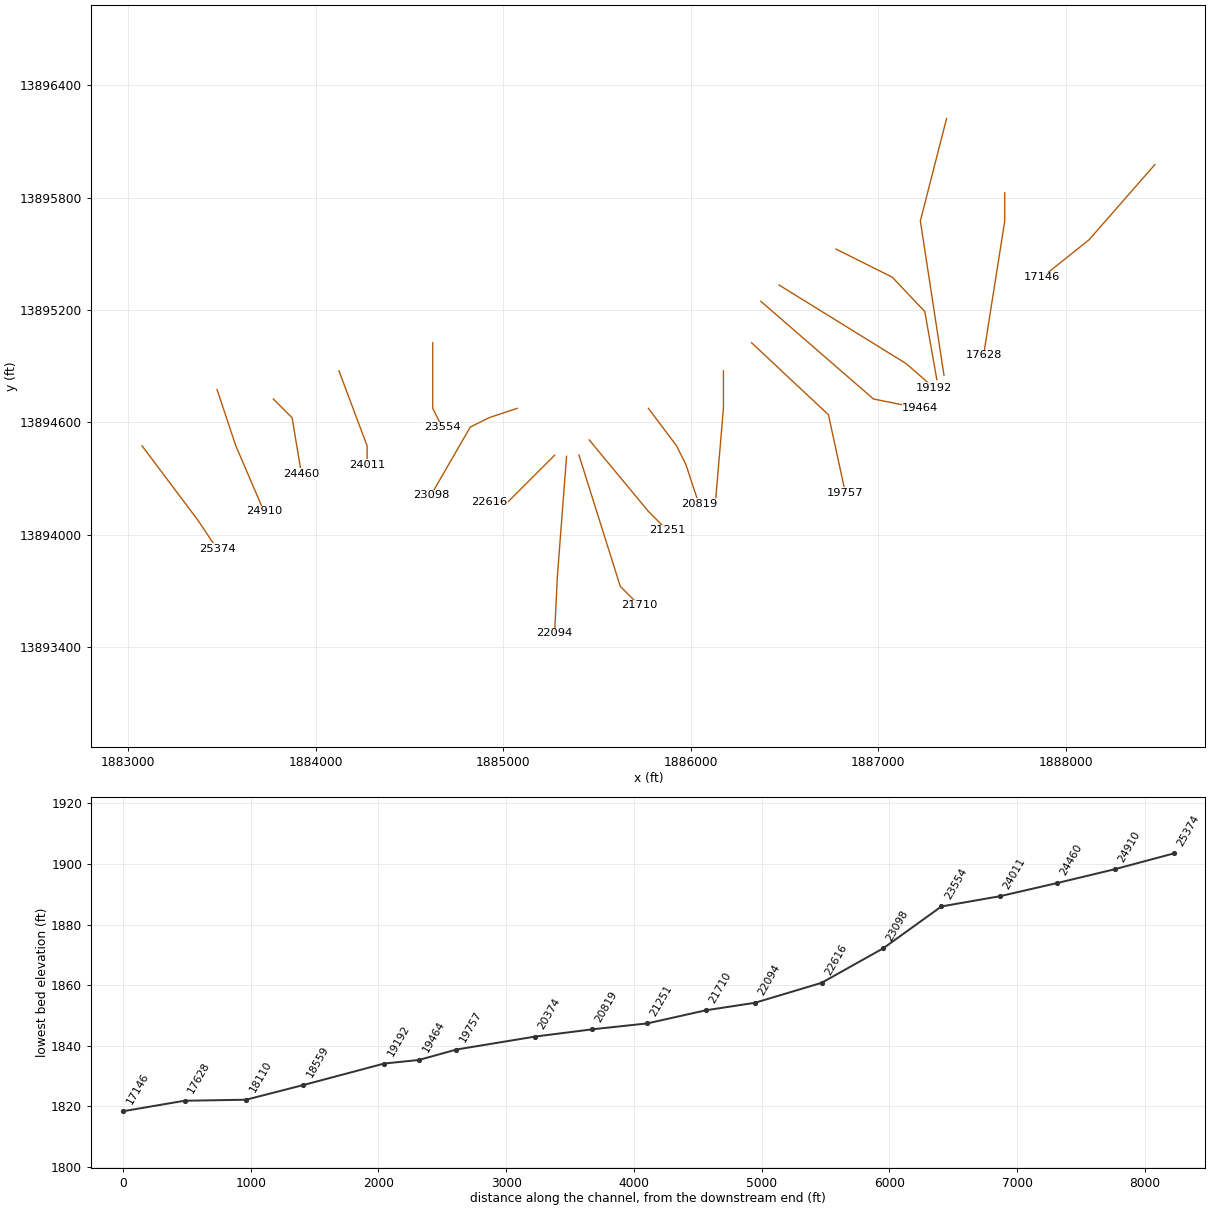
HEC-RAS study Bushwhack Creek.prj: Bushwhack Creek Base Level Engineering

--- Bushwhack Creek.g01 (geometry) --- (continued)

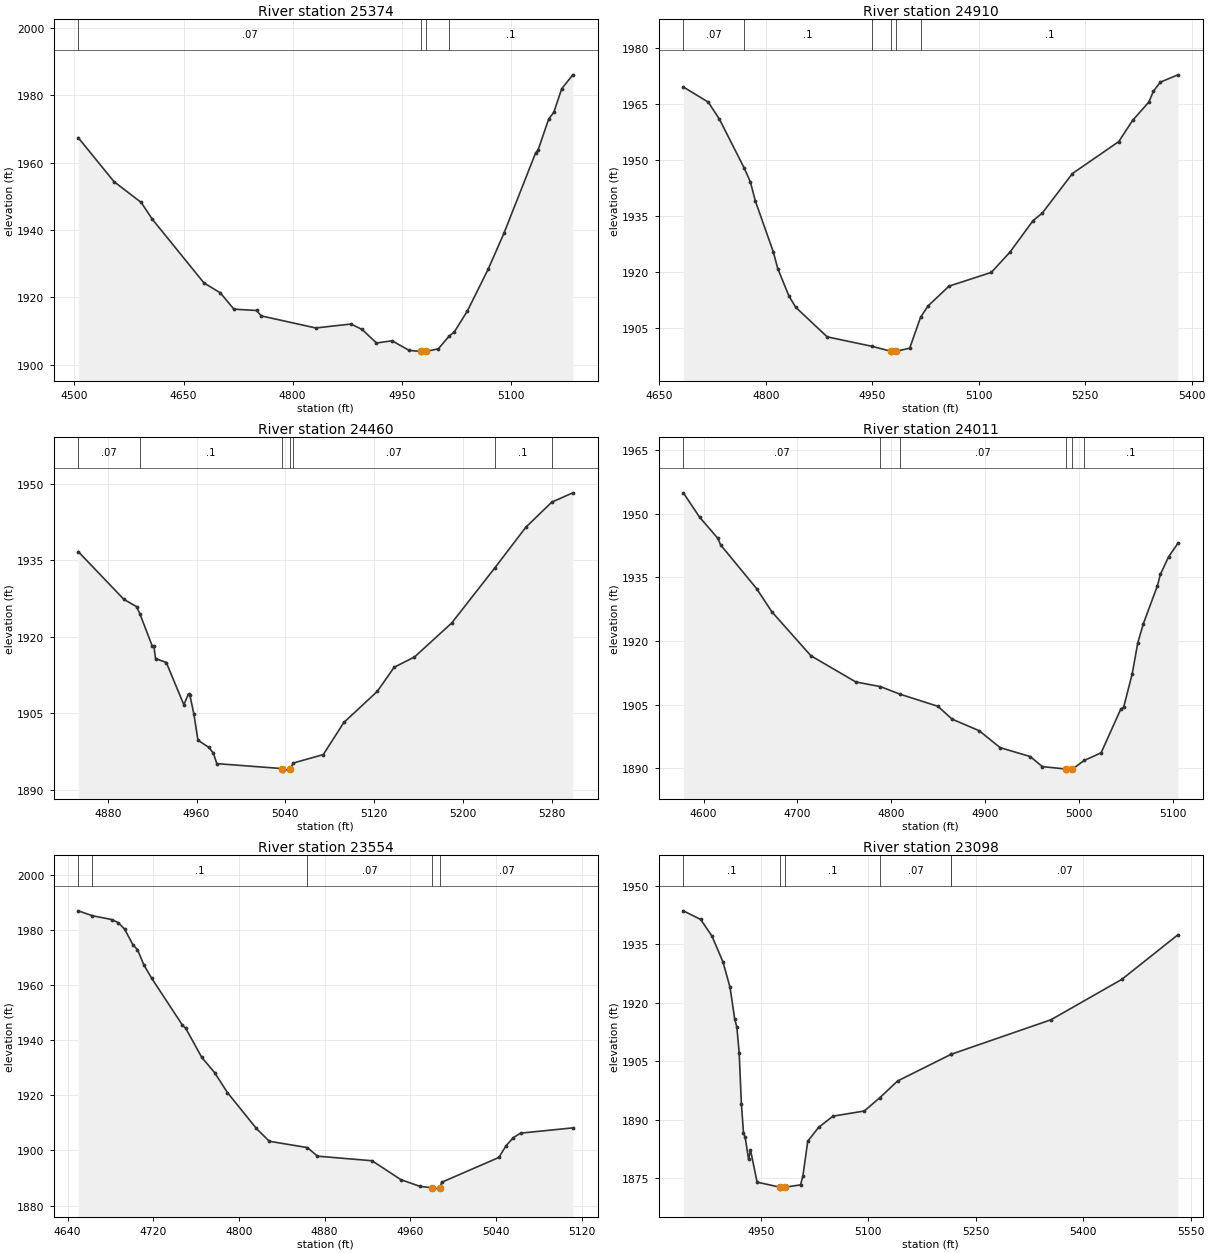
Type RM Length L Ch R = 1 ,25374   ,464,464,464
BEGIN DESCRIPTION:
Bushwhack Creek 51.0
END DESCRIPTION:
XS GIS Cut Line= 3
      1883074.97     13894475.04        1883375.       13894075.
      1883474.98     13893925.02
#Sta/Elev= 30
  4505.2 1967.42  4554.3 1954.38  4591.8 1948.19  4606.8 1943.28  4678.1  1924.3
  4700.6 1921.35  4719.3 1916.51  4750.4 1916.12  4756.8 1914.52  4831.8 1910.93
  4880.4  1912.1  4895.6 1910.48  4915.4 1906.47  4936.8 1907.12  4960.4 1904.28
  4976.8 1903.96  4977.3 1903.46  4983.9 1903.96  5000.6 1904.76  5015.5 1908.56
  5022.4 1909.73  5040.4 1915.96  5069.3  1928.5  5090.9 1939.14  5134.2 1962.85
  5137.8 1963.82  5152.2 1972.92  5159.4 1974.99  5170.2 1981.98  5185.5 1986.08
#Mann= 4 ,-1 , 0
  4505.2     .07       0  4976.8     .05       0  4983.9     .07       0
  5015.5      .1       0
Bank Sta=4976.8,4983.9
XS Rating Curve= 0 ,0
Exp/Cntr=0.3,0.1

Type RM Length L Ch R = 1 ,24910   ,450,450,450
BEGIN DESCRIPTION:
Bushwhack Creek 50.0
END DESCRIPTION:
XS GIS Cut Line= 3
      1883474.99     13894775.03        1883575.       13894475.
      1883724.98     13894125.04
#Sta/Elev= 30
  4683.7 1969.65  4718.8  1965.6  4734.6 1960.99  4769.6 1947.85  4778.1  1944.2
  4785.2 1939.04  4810.5 1925.39  4816.8 1920.89  4832.6 1913.51  4842.1 1910.53
  4886.4  1902.6  4949.7 1900.05  4976.1 1898.73  4976.6 1898.23  4983.3 1898.73
  5002.7 1899.56    5018 1907.86  5028.4 1910.87  5058.1 1916.21  5117.7  1919.9
  5143.9 1925.32  5176.5 1933.79  5189.5  1935.8    5232 1946.43  5297.3    1955
  5316.8 1960.69  5339.7 1965.61  5346.2 1968.54    5356 1970.96  5380.7 1972.92
#Mann= 6 ,-1 , 0
  4683.7     .07       0  4769.6      .1       0  4949.7     .07       0
  4976.1     .05       0  4983.3     .07       0    5018      .1       0
Bank Sta=4976.1,4983.3
XS Rating Curve= 0 ,0
Exp/Cntr=0.3,0.1

Type RM Length L Ch R = 1 ,24460   ,449,449,449
BEGIN DESCRIPTION:
Bushwhack Creek 49.0
END DESCRIPTION:
XS GIS Cut Line= 3
      1883775.03     13894724.97        1883875.       13894625.
        1883925.     13894325.01
#Sta/Elev= 30
  4853.4 1936.68  4894.5 1927.33    4906 1925.89  4909.1 1924.38  4919.9 1918.26
  4921.5 1918.17    4923 1915.73  4932.7 1914.96  4948.5 1906.68  4952.7 1908.84
  4953.9 1908.58  4957.5 1904.92  4961.2 1899.74  4970.9 1898.35  4975.1  1897.2
  4978.2 1895.15    5037 1894.18  5037.5 1893.68  5044.4 1894.18  5047.1 1895.27
  5074.1 1896.92  5092.6 1903.21  5122.8 1909.31    5138 1914.04  5156.2 1916.03
  5189.7 1922.68  5228.5 1933.46  5256.5 1941.45  5279.9 1946.37  5298.9  1948.2
#Mann= 7 ,-1 , 0
  4853.4     .07       0  4909.1      .1       0    5037     .05       0
  5044.4      .1       0  5047.1     .07       0  5228.5      .1       0
  5279.9     .07       0
Bank Sta=5037,5044.4
XS Rating Curve= 0 ,0
Exp/Cntr=0.3,0.1

Type RM Length L Ch R = 1 ,24011   ,457,457,457
BEGIN DESCRIPTION:
Bushwhack Creek 48.0
END DESCRIPTION:
XS GIS Cut Line= 3
      1884125.01     13894874.97        1884275.       13894475.
        1884275.     13894374.97
#Sta/Elev= 30
  4578.5 1954.87  4595.8 1949.14  4615.1  1944.2  4618.3 1942.59  4656.7 1932.28
  4672.7 1926.89  4714.4 1916.51  4762.4 1910.32  4788.5 1909.24  4809.7 1907.43
  4849.8  1904.6    4865 1901.57  4893.8 1898.85  4916.2 1894.86  4948.3 1892.76
  4961.1  1890.4  4985.9 1889.83  4986.4 1889.33  4993.3 1889.83  5005.9 1891.85
  5023.8 1893.64  5044.8 1903.96  5047.8 1904.36  5056.9 1912.19  5062.9 1919.54
  5068.8 1924.03  5083.9 1933.03    5087 1935.69  5095.8 1939.82  5105.7 1942.99
#Mann= 6 ,-1 , 0
  4578.5     .07       0  4788.5      .1       0  4809.7     .07       0
  4985.9     .05       0  4993.3     .07       0  5005.9      .1       0
Bank Sta=4985.9,4993.3
XS Rating Curve= 0 ,0
Exp/Cntr=0.3,0.1

Type RM Length L Ch R = 1 ,23554   ,456,456,456
BEGIN DESCRIPTION:
Bushwhack Creek 47.0
END DESCRIPTION:
XS GIS Cut Line= 3
        1884625.     13895025.04        1884625.       13894675.
      1884674.98     13894575.04
#Sta/Elev= 30
    4650 1986.84  4663.2 1985.06  4681.3 1983.68  4687.3 1982.57  4693.3 1980.19
  4701.2 1974.43  4705.3 1972.78  4711.3  1967.2  4718.4 1962.49  4747.3 1945.39
  4750.3  1944.3  4765.3 1933.73  4777.3  1928.2  4789.3 1920.95  4816.3 1907.96
  4828.3 1903.32    4864 1901.01  4873.3 1897.91  4924.3 1896.25  4951.3 1889.38
  4969.3 1886.93  4980.5 1886.46    4981 1885.96    4988 1886.46  4989.2 1888.43
  5042.7 1897.43  5049.4 1901.68  5056.1 1904.58    5063 1906.25  5111.8 1908.17
#Mann= 5 ,-1 , 0
    4650     .07       0  4663.2      .1       0    4864     .07       0
  4980.5     .05       0    4988     .07       0
Bank Sta=4980.5,4988
XS Rating Curve= 0 ,0
Exp/Cntr=0.3,0.1

Type RM Length L Ch R = 1 ,23098   ,482,482,482
BEGIN DESCRIPTION:
Bushwhack Creek 46.0
END DESCRIPTION:
XS GIS Cut Line= 4
      1885074.97     13894674.99        1884925.       13894625.
        1884825.       13894575.      1884614.86     13894210.87
#Sta/Elev= 30
    4842 1943.65  4866.1 1941.44  4881.9 1937.17  4897.4 1930.47  4907.2 1923.95
  4913.6 1915.91  4916.7 1913.73  4919.9 1907.12    4923 1894.05  4925.9 1886.69
  4928.3 1885.42    4933 1879.81  4935.7 1882.22  4944.9 1873.94  4976.7 1872.64
  4977.2 1872.14  4984.2 1872.64  5005.6 1873.24  5008.9 1875.59  5015.6 1884.44
  5030.8 1888.02  5050.9 1890.89  5094.6 1892.22    5116  1895.6  5141.1 1899.94
  5215.7 1906.78  5215.9  1906.8  5355.1 1915.66  5453.9 1926.03  5532.3  1937.5
#Mann= 6 ,-1 , 0
    4842      .1       0  4976.7     .05       0  4984.2      .1       0
    5116     .07       0  5215.7      .1       0  5215.9     .07       0
Bank Sta=4976.7,4984.2
XS Rating Curve= 0 ,0
Exp/Cntr=0.3,0.1

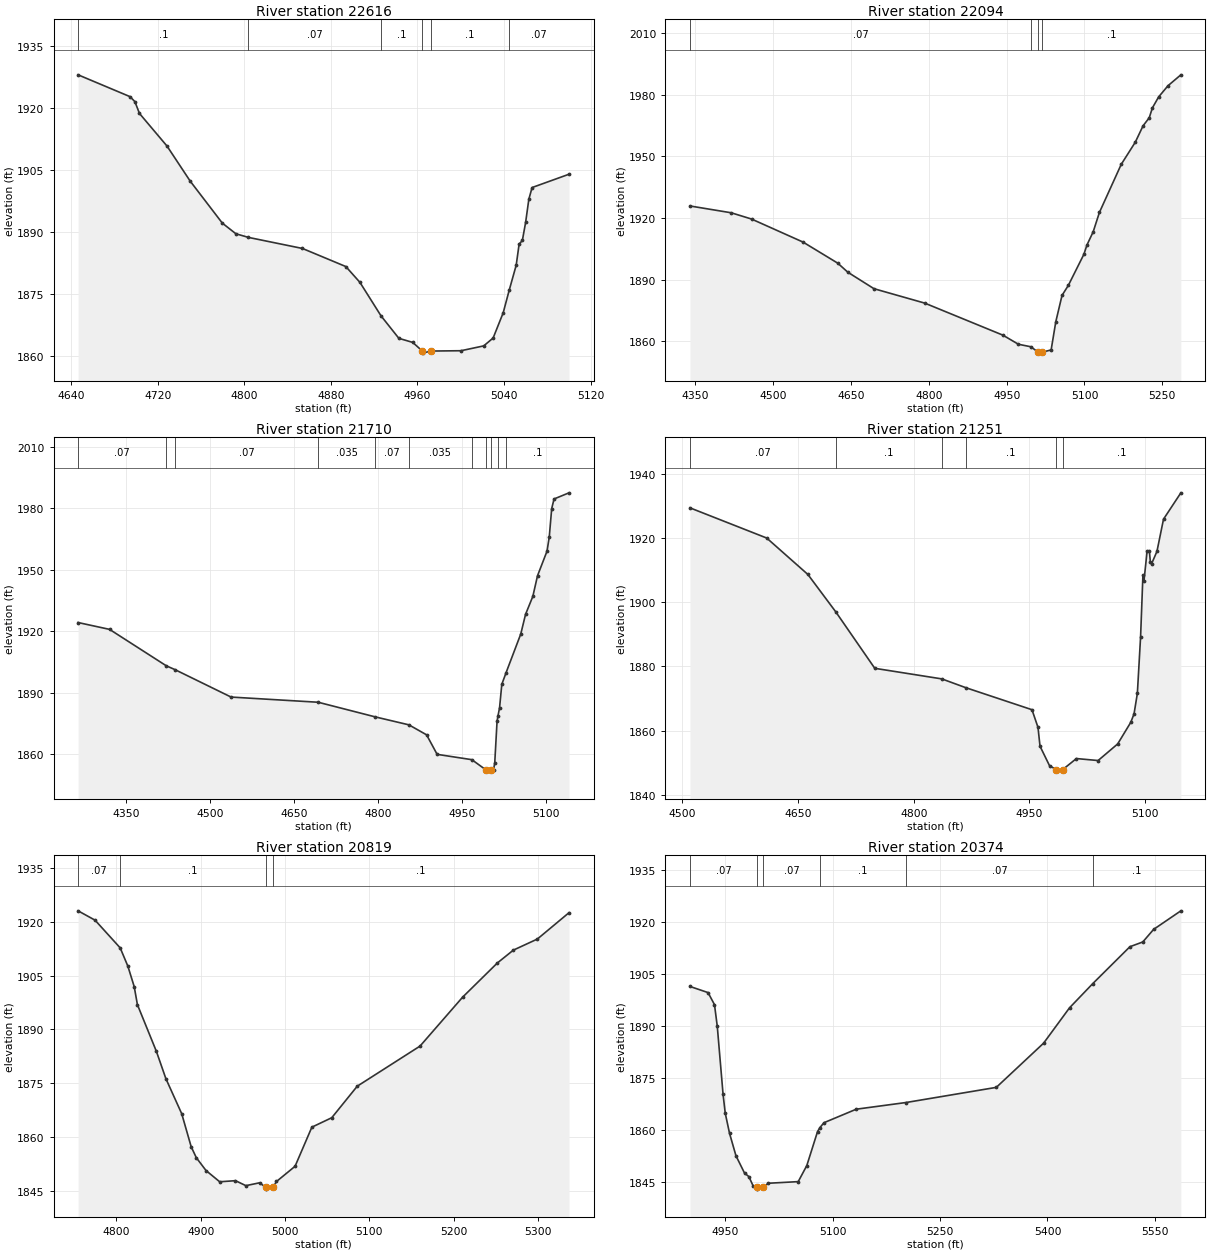
Type RM Length L Ch R = 1 ,22616   ,522,522,522
BEGIN DESCRIPTION:
Bushwhack Creek 45.0
END DESCRIPTION:
XS GIS Cut Line= 3
      1885275.03     13894425.03        1885025.       13894175.
        1884925.       13894175.
#Sta/Elev= 30
  4646.4 1927.95  4694.4 1922.68  4698.9 1921.47  4703.1 1918.63  4728.6 1910.74
    4750 1902.28  4779.7 1892.14  4792.2 1889.58  4803.8  1888.7  4853.7 1886.03
  4893.8 1881.66  4906.8 1877.85  4926.3 1869.76  4942.8 1864.33  4955.6 1863.35
  4964.5 1861.26    4965 1860.76  4972.1 1861.26  5000.2 1861.34  5021.2 1862.51
  5029.9 1864.41  5039.2 1870.51  5044.8    1876  5051.2 1881.98  5053.9 1887.07
  5056.9 1887.96  5059.9  1892.3  5062.9 1897.93  5065.9 1900.74    5100 1903.95
#Mann= 6 ,-1 , 0
  4646.4      .1       0  4803.8     .07       0  4926.3      .1       0
  4964.5     .05       0  4972.1      .1       0  5044.8     .07       0
Bank Sta=4964.5,4972.1
XS Rating Curve= 0 ,0
Exp/Cntr=0.3,0.1

Type RM Length L Ch R = 1 ,22094   ,384,384,384
BEGIN DESCRIPTION:
Bushwhack Creek 44.0
END DESCRIPTION:
XS GIS Cut Line= 3
      1885338.52     13894419.14      1885289.71     13893780.85
        1885275.     13893474.95
#Sta/Elev= 30
  4339.5 1925.81  4419.1 1922.49  4458.2 1919.45  4557.5 1908.23  4624.4 1897.97
    4644 1893.53  4694.3 1885.53  4792.1 1878.52  4942.7 1862.93  4972.7 1858.49
  4996.8 1857.26  5010.5 1854.67    5011 1854.17  5019.1 1854.67  5035.8 1855.72
  5044.8 1869.47  5056.8 1882.27  5068.9 1887.12  5098.9 1902.26  5104.9 1906.83
  5116.9 1913.26  5128.9 1922.68    5171  1946.1    5198 1956.84    5213 1964.82
    5225 1968.78    5231 1973.56  5243.1 1978.91  5261.1 1984.35  5285.9 1989.65
#Mann= 4 ,-1 , 0
  4339.5     .07       0  4996.8      .1       0  5010.5     .05       0
  5019.1      .1       0
Bank Sta=5010.5,5019.1
XS Rating Curve= 0 ,0
Exp/Cntr=0.3,0.1

Type RM Length L Ch R = 1 ,21710   ,459,459,459
BEGIN DESCRIPTION:
Bushwhack Creek 43.0
END DESCRIPTION:
XS GIS Cut Line= 3
      1885404.37     13894426.34        1885625.       13893725.
      1885724.97     13893625.03
#Sta/Elev= 30
  4264.5 1924.25  4320.7 1920.91  4422.1 1903.11  4437.5 1901.26  4537.7 1887.86
  4693.2 1885.33  4795.3 1878.17  4855.2  1874.3  4886.8 1869.42  4905.6 1859.89
  4967.6 1857.29  4993.3  1852.2  4993.8  1851.7    5002  1852.2  5006.3 1852.27
  5008.5 1855.73  5012.6 1875.95  5014.3 1878.72  5017.1 1882.62  5021.1 1894.07
  5028.6 1899.67    5055 1918.69  5063.5 1928.25  5076.5 1937.01  5084.9 1947.13
  5101.9 1959.15  5105.9 1966.19  5110.2 1979.92  5114.4 1984.58  5141.1 1987.58
#Mann= 11 ,-1 , 0
  4264.5     .07       0  4422.1      .1       0  4437.5     .07       0
  4693.2    .035       0  4795.3     .07       0  4855.2    .035       0
  4967.6      .1       0  4993.3     .05       0    5002      .1       0
  5014.3    .035       0  5028.6      .1       0
Bank Sta=4993.3,5002
XS Rating Curve= 0 ,0
Exp/Cntr=0.3,0.1

Type RM Length L Ch R = 1 ,21251   ,432,432,432
BEGIN DESCRIPTION:
Bushwhack Creek 42.0
END DESCRIPTION:
XS GIS Cut Line= 3
      1885459.46     13894506.38        1885775.       13894125.
      1885874.99     13894025.01
#Sta/Elev= 30
  4509.9 1929.44  4609.4 1920.03  4662.8 1908.67    4699    1897  4749.5 1879.42
  4836.4 1876.12  4867.5 1873.38  4953.3 1866.51  4961.1    1861  4963.7 1855.14
    4976 1849.08  4984.5 1847.87    4985 1847.37  4993.2 1847.87  5010.9 1851.29
    5039 1850.67  5064.4 1855.85  5081.4  1862.6  5085.6 1865.22  5089.9  1871.6
  5094.1  1889.3  5097.1  1908.4  5098.4 1906.49  5102.6 1916.08  5105.5 1915.88
  5106.8 1912.47  5108.5 1912.09  5115.3 1915.87  5123.8 1925.91  5146.3 1934.12
#Mann= 6 ,-1 , 0
  4509.9     .07       0    4699      .1       0  4836.4     .07       0
  4867.5      .1       0  4984.5     .05       0  4993.2      .1       0
Bank Sta=4984.5,4993.2
XS Rating Curve= 0 ,0
Exp/Cntr=0.3,0.1

Type RM Length L Ch R = 1 ,20819   ,445,445,445
BEGIN DESCRIPTION:
Bushwhack Creek 41.0
END DESCRIPTION:
XS GIS Cut Line= 4
      1885775.02     13894674.97        1885925.       13894475.
        1885975.       13894375.      1886043.67     13894166.07
#Sta/Elev= 30
  4754.8 1923.11  4774.9  1920.5  4804.7 1912.76  4813.8 1907.65  4821.3 1901.95
  4825.1 1896.91  4847.6 1883.86  4858.8 1876.27  4877.6 1866.46  4888.8 1857.25
  4894.9 1854.18  4906.4  1850.6  4922.6 1847.46  4941.3 1847.77  4953.6 1846.38
  4969.9 1847.18  4977.1 1845.91  4977.6 1845.41  4985.8 1845.91  4989.9 1847.54
  5011.9 1851.79  5031.8 1862.71  5055.4 1865.35  5085.6 1874.15    5160 1885.35
  5210.5 1899.02  5251.6 1908.55  5270.5 1912.13    5299 1915.23  5336.5 1922.59
#Mann= 4 ,-1 , 0
  4754.8     .07       0  4804.7      .1       0  4977.1     .05       0
  4985.8      .1       0
Bank Sta=4977.1,4985.8
XS Rating Curve= 0 ,0
Exp/Cntr=0.3,0.1

Type RM Length L Ch R = 1 ,20374   ,617,617,617
BEGIN DESCRIPTION:
Bushwhack Creek 40.0
END DESCRIPTION:
XS GIS Cut Line= 4
        1886175.     13894874.99        1886175.       13894775.
        1886175.       13894675.      1886133.71     13894190.75
#Sta/Elev= 30
  4900.4 1901.43  4925.7 1899.66  4934.7 1896.18  4938.6 1889.92  4946.7  1870.3
  4949.7 1864.93  4955.7 1859.13  4964.7 1852.64  4976.7 1847.64  4982.7 1846.65
  4988.7 1843.96  4994.2 1843.53  4994.7 1843.03    5003 1843.53  5009.7 1844.72
  5051.7 1845.19  5063.7 1849.82  5078.7 1859.61  5082.1 1860.78  5087.7 1862.17
  5132.8 1866.06  5202.5 1867.99  5328.5 1872.35  5394.6 1885.09  5430.8 1895.27
  5463.3 1902.25  5515.2 1912.88  5533.2 1914.25  5548.3 1917.87  5586.4 1923.22
#Mann= 6 ,-1 , 0
  4900.4     .07       0  4994.2     .05       0    5003     .07       0
  5082.1      .1       0  5202.5     .07       0  5463.3      .1       0
Bank Sta=4994.2,5003
XS Rating Curve= 0 ,0
Exp/Cntr=0.3,0.1

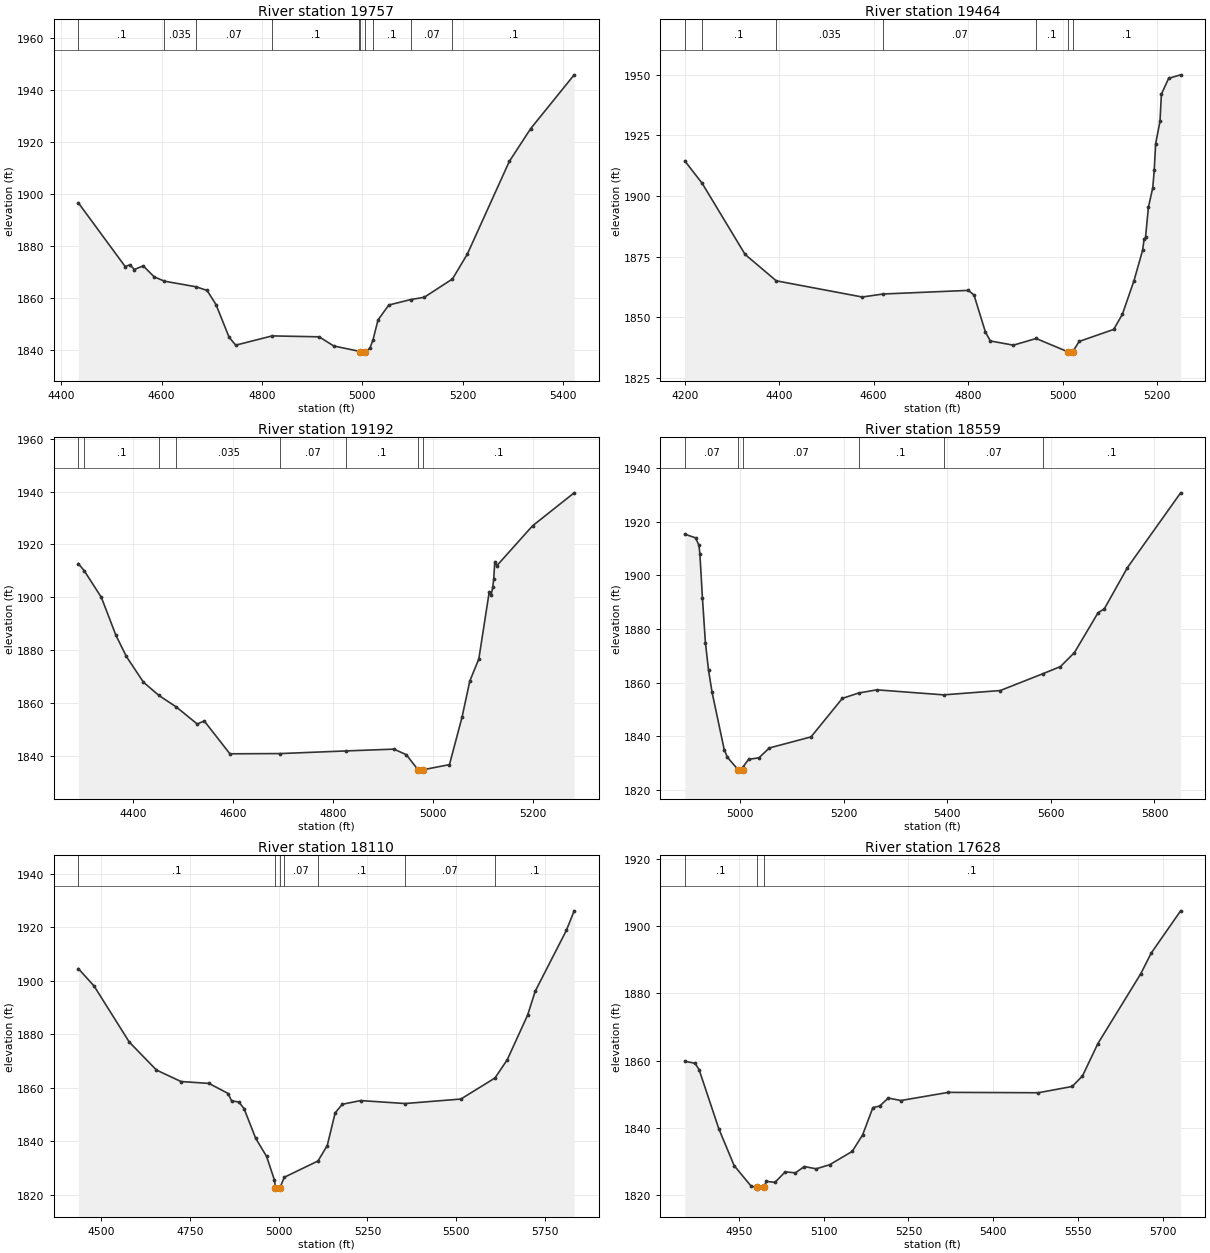
Type RM Length L Ch R = 1 ,19757   ,293,293,293
BEGIN DESCRIPTION:
Bushwhack Creek 39.0
END DESCRIPTION:
XS GIS Cut Line= 3
      1886324.99     13895025.01      1886734.79     13894641.08
        1886825.       13894225.
#Sta/Elev= 30
  4434.3 1896.52  4527.6 1872.02  4537.1 1872.69  4545.9 1870.87  4563.4  1872.3
  4585.3 1868.07  4605.7  1866.4  4668.4 1864.26  4690.7 1862.84  4708.5 1857.39
  4734.5 1844.85  4747.7 1841.81  4820.2 1845.37    4914 1845.02  4942.8  1841.5
  4992.5  1839.5  4995.5 1839.25    4996 1838.75    5005 1839.25  5014.9 1840.65
  5021.2 1843.95    5031 1851.49  5052.5 1857.24    5096 1859.33  5123.1 1860.21
  5179.3 1867.26  5208.9 1876.81  5292.4  1912.4  5334.9    1925  5421.6  1945.7
#Mann= 10 ,-1 , 0
  4434.3      .1       0  4605.7    .035       0  4668.4     .07       0
  4820.2      .1       0  4992.5     .07       0  4995.5     .05       0
    5005     .07       0  5021.2      .1       0    5096     .07       0
  5179.3      .1       0
Bank Sta=4995.5,5005
XS Rating Curve= 0 ,0
Exp/Cntr=0.3,0.1

Type RM Length L Ch R = 1 ,19464   ,272,272,272
BEGIN DESCRIPTION:
Bushwhack Creek 38.0
END DESCRIPTION:
XS GIS Cut Line= 3
       1886374.6     13895246.09        1886975.       13894725.
      1887224.95     13894675.01
#Sta/Elev= 30
  4200.2  1914.5    4237 1905.27    4328 1875.95  4393.9  1865.1    4576 1858.43
    4620 1859.67  4800.7 1861.16  4812.6 1859.23  4836.9 1843.93  4847.3 1840.32
    4896 1838.59  4944.2 1841.34  5011.9 1835.81  5012.4 1835.31  5021.4 1835.81
  5035.1 1840.12  5108.4 1845.08  5126.8 1851.34  5151.3 1865.13  5169.7 1877.75
  5172.7 1882.18  5175.8 1883.01  5181.9 1895.45  5191.1 1903.43  5194.2 1910.63
  5197.2 1921.59  5206.4 1930.81  5209.4 1942.01  5224.7 1948.52  5250.1 1949.97
#Mann= 7 ,-1 , 0
  4200.2     .07       0    4237      .1       0  4393.9    .035       0
    4620     .07       0  4944.2      .1       0  5011.9     .05       0
  5021.4      .1       0
Bank Sta=5011.9,5021.4
XS Rating Curve= 0 ,0
Exp/Cntr=0.3,0.1

Type RM Length L Ch R = 1 ,19192   ,633,633,633
BEGIN DESCRIPTION:
Bushwhack Creek 37.0
END DESCRIPTION:
XS GIS Cut Line= 3
      1886471.29     13895333.23      1887149.52     13894913.62
      1887295.77     13894786.07
#Sta/Elev= 30
    4290 1912.69  4301.7 1910.04    4336 1899.95  4365.1 1885.61  4386.1 1877.54
  4420.3 1867.79  4451.2 1862.78  4486.2 1858.39  4527.8 1851.97  4541.8 1853.13
  4593.1 1840.69  4694.2 1840.78  4825.5 1841.78  4921.2 1842.46  4945.9 1840.36
  4969.4 1834.63  4969.9 1834.13  4978.9 1834.63  5032.2  1836.6  5057.4 1854.58
  5072.9 1868.24    5091 1876.66  5111.7 1901.92  5115.5 1900.66  5118.8 1903.84
  5120.8  1906.9  5122.8 1913.13  5126.8 1911.88  5198.4 1927.02  5281.6 1939.51
#Mann= 8 ,-1 , 0
    4290     .07       0  4301.7      .1       0  4451.2     .07       0
  4486.2    .035       0  4694.2     .07       0  4825.5      .1       0
  4969.4     .05       0  4978.9      .1       0
Bank Sta=4969.4,4978.9
XS Rating Curve= 0 ,0
Exp/Cntr=0.3,0.1

Type RM Length L Ch R = 1 ,18559   ,449,449,449
BEGIN DESCRIPTION:
Bushwhack Creek 36.0
END DESCRIPTION:
XS GIS Cut Line= 5
      1886774.99       13895525.        1886875.       13895475.
        1887075.       13895375.      1887248.68     13895191.51
      1887312.92     13894827.71
#Sta/Elev= 30
    4893 1915.38  4913.7 1914.04  4920.4 1911.24  4922.2 1907.84  4927.1 1891.49
  4932.8 1874.94  4938.9 1864.57  4945.7  1856.4  4969.1 1835.09  4975.3 1832.21
  4996.1 1827.54  4996.6 1827.04  5005.7 1827.54    5006 1828.75  5016.1 1831.43
  5036.2 1832.02  5056.3 1835.68  5136.8 1839.81  5197.2 1854.16  5228.5 1856.16
    5264 1857.35  5392.8 1855.48  5502.2 1857.09  5585.3 1863.42  5618.4 1866.03
  5645.3  1871.2    5691 1886.08  5703.2 1887.58  5747.9 1902.96  5850.5 1930.81
#Mann= 6 ,-1 , 0
    4893     .07       0  4996.1     .05       0  5005.7     .07       0
  5228.5      .1       0  5392.8     .07       0  5585.3      .1       0
Bank Sta=4996.1,5005.7
XS Rating Curve= 0 ,0
Exp/Cntr=0.3,0.1

Type RM Length L Ch R = 1 ,18110   ,482,482,482
BEGIN DESCRIPTION:
Bushwhack Creek 35.0
END DESCRIPTION:
XS GIS Cut Line= 3
      1887364.87     13896221.89        1887225.       13895675.
      1887350.94     13894852.17
#Sta/Elev= 30
  4435.5 1904.53    4480    1898  4579.1 1877.08  4655.7 1866.64  4724.8 1862.36
  4803.5 1861.66  4857.8 1857.88  4867.1 1855.13  4887.5 1854.73  4902.3 1852.27
  4935.2 1841.16  4965.8 1834.42  4987.9 1825.64  4990.9 1822.69  4991.4 1822.19
  5003.5 1822.69  5015.6 1826.61  5110.7  1832.7  5136.8 1838.47  5159.1 1850.68
  5179.3 1853.88  5230.9 1855.25  5356.2 1854.15  5513.2 1855.82  5609.3 1863.68
  5643.7 1870.45  5701.3 1887.16  5722.6 1896.05  5810.6 1918.83  5832.4 1926.09
#Mann= 7 ,-1 , 0
  4435.5      .1       0  4990.9     .05       0  5003.5      .1       0
  5015.6     .07       0  5110.7      .1       0  5356.2     .07       0
  5609.3      .1       0
Bank Sta=4990.9,5003.5
XS Rating Curve= 0 ,0
Exp/Cntr=0.3,0.1

Type RM Length L Ch R = 1 ,17628   ,482,482,482
BEGIN DESCRIPTION:
Bushwhack Creek 34.0
END DESCRIPTION:
XS GIS Cut Line= 3
        1887675.       13895825.        1887675.       13895675.
      1887561.92     13894957.25
#Sta/Elev= 30
  4854.6 1859.85  4872.9 1859.22  4879.8 1857.39  4914.9 1839.72  4941.9 1828.83
  4971.9 1822.73  4981.4 1822.35  4981.9 1821.85  4994.1 1822.35  4998.9 1824.17
    5014 1823.86  5032.2 1826.99  5050.2 1826.69    5066 1828.56  5086.9 1827.89
  5110.6 1829.09  5150.6 1833.06  5168.9 1837.94  5187.1 1846.06  5199.2 1846.55
  5214.4 1848.91  5236.5 1848.18  5320.7  1850.6  5479.7 1850.49  5539.4 1852.35
  5557.6 1855.45  5584.9 1865.09  5660.9  1885.9  5679.1 1891.96  5731.2 1904.54
#Mann= 3 ,-1 , 0
  4854.6      .1       0  4981.4     .05       0  4994.1      .1       0
Bank Sta=4981.4,4994.1
XS Rating Curve= 0 ,0
Exp/Cntr=0.3,0.1

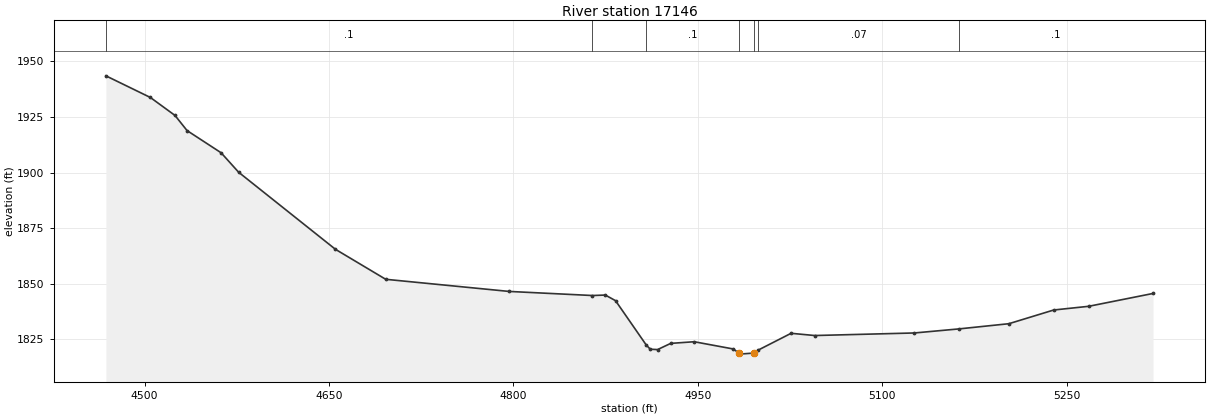
Type RM Length L Ch R = 1 ,17146   ,451,451,451
BEGIN DESCRIPTION:
Bushwhack Creek 33.0
END DESCRIPTION:
XS GIS Cut Line= 3
      1888475.01     13895975.01        1888125.       13895575.
      1887874.98     13895374.98
#Sta/Elev= 30
  4468.5 1943.47  4504.7 1933.73  4524.7 1925.67  4534.5 1918.87  4562.2 1908.89
  4576.5 1900.12  4655.2  1865.5  4696.1 1852.02  4796.4 1846.57  4864.2 1844.73
  4874.7 1844.94    4883 1842.42    4908 1822.48  4911.3 1820.59  4917.2 1820.43
  4927.9 1823.22    4947 1823.96  4978.9 1820.69  4983.2 1818.89  4983.7 1818.39
  4995.9 1818.89  4998.6 1820.08  5025.8 1827.75    5045 1826.75  5126.1  1827.9
  5162.4 1829.73  5202.9 1832.06  5239.4 1838.22  5267.8 1839.88  5320.2 1845.66
#Mann= 7 ,-1 , 0
  4468.5      .1       0  4864.2     .07       0    4908      .1       0
  4983.2     .05       0  4995.9      .1       0  4998.6     .07       0
  5162.4      .1       0
Bank Sta=4983.2,4995.9
XS Rating Curve= 0 ,0
Exp/Cntr=0.3,0.1