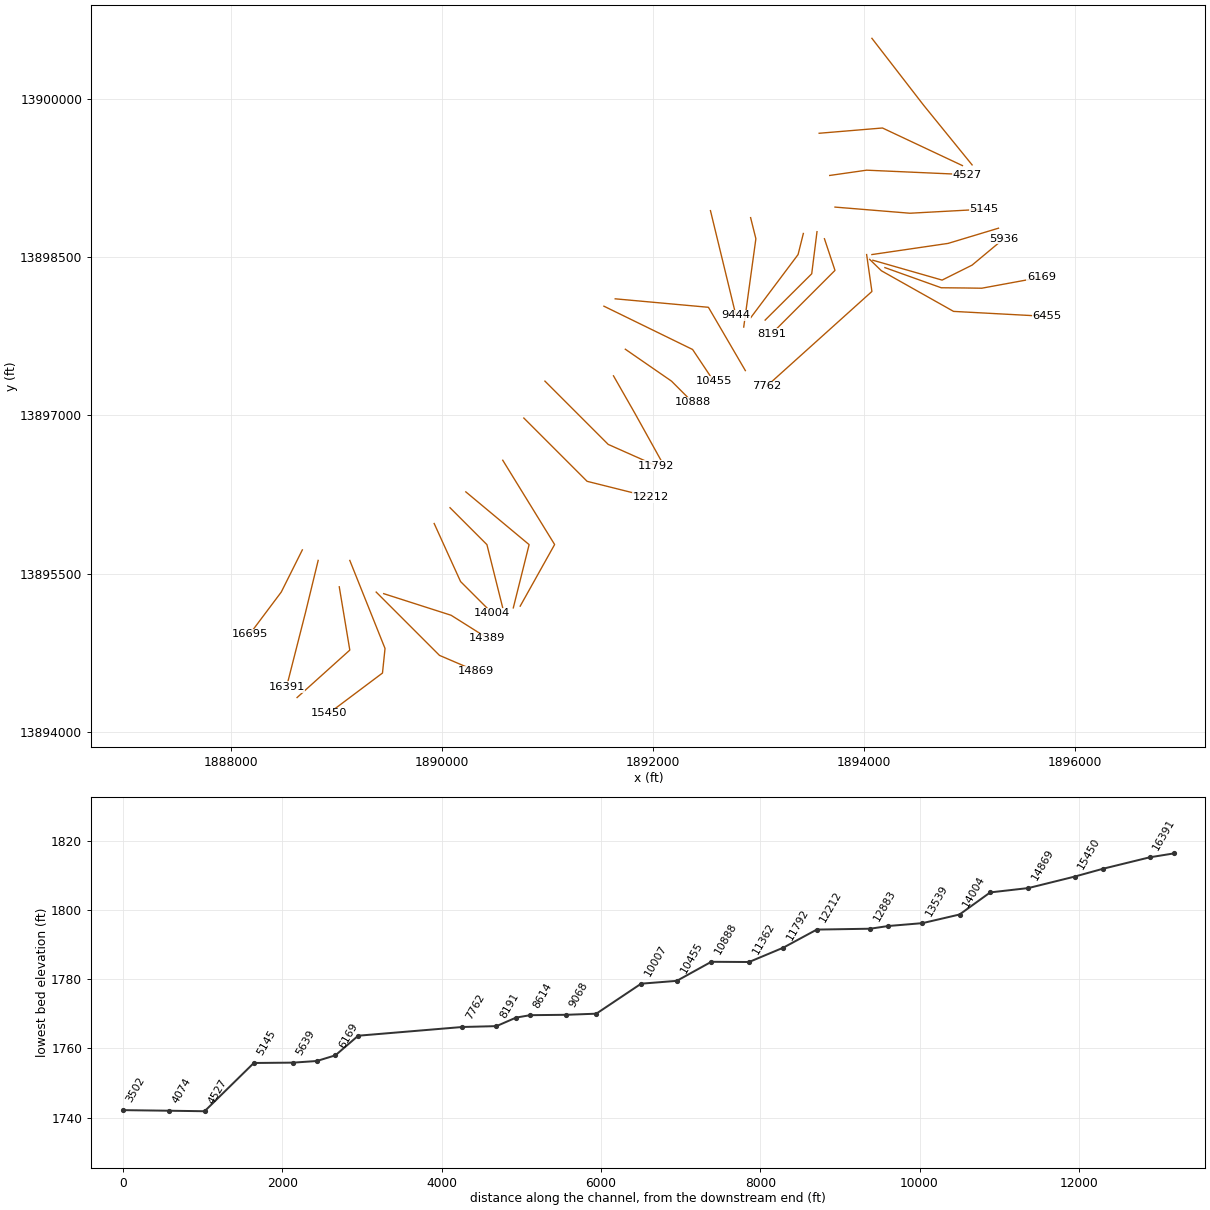
HEC-RAS study Bushwhack Creek.prj: Bushwhack Creek Base Level Engineering

--- Bushwhack Creek.g01 (geometry) --- (continued)

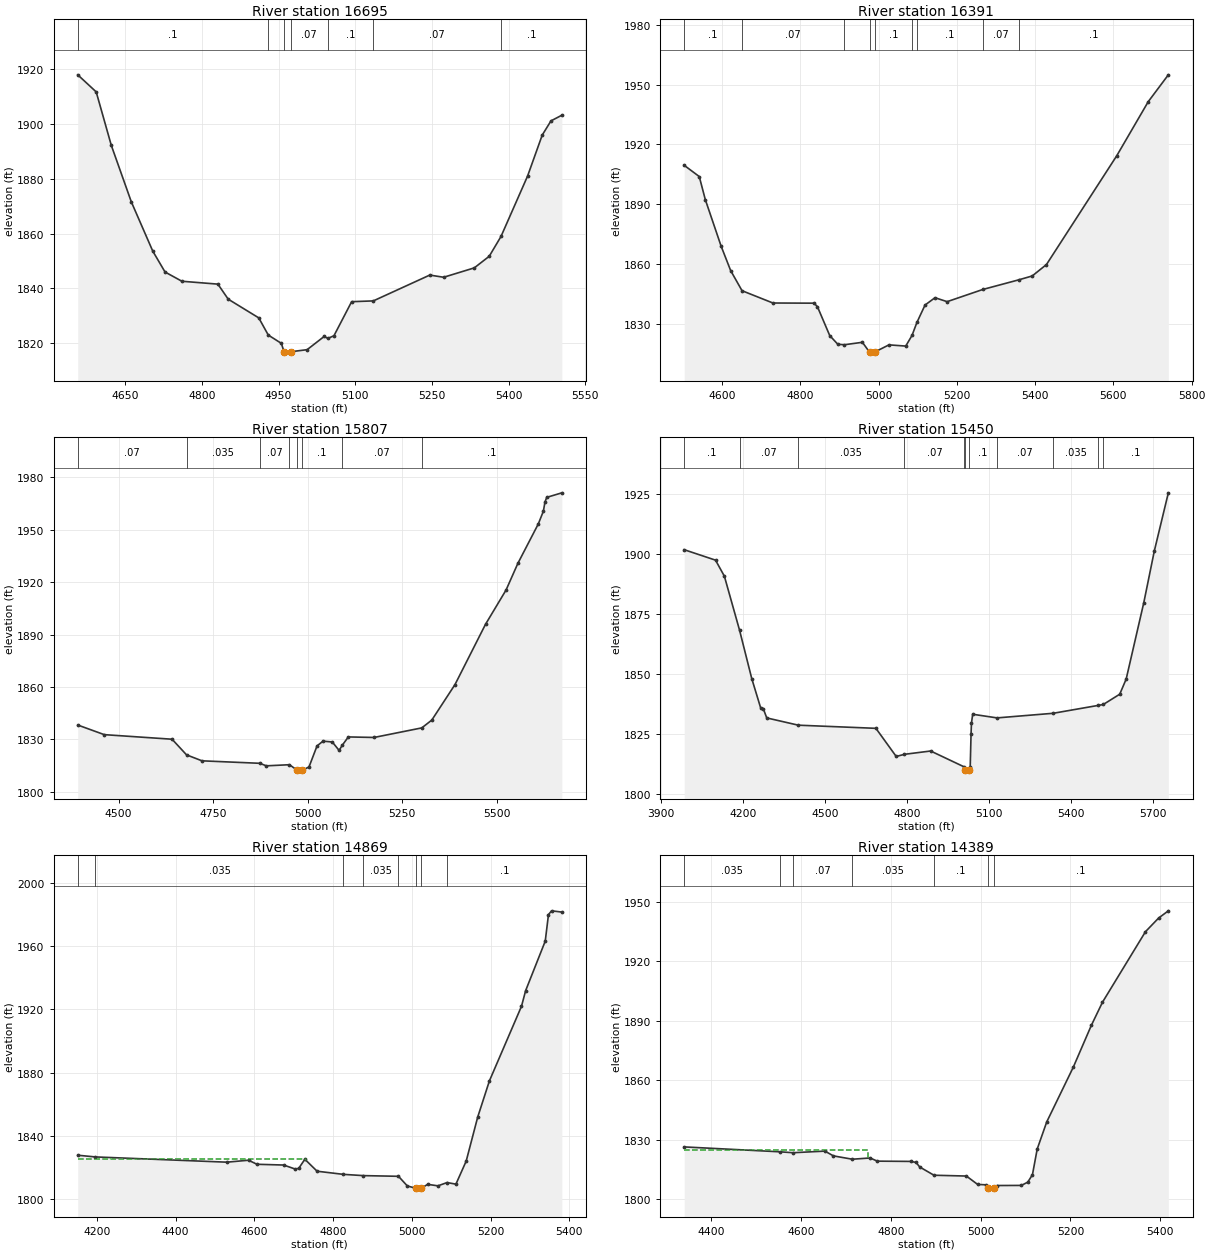
Type RM Length L Ch R = 1 ,16695   ,304,304,304
BEGIN DESCRIPTION:
Bushwhack Creek 32.0
END DESCRIPTION:
XS GIS Cut Line= 3
      1888675.01     13895725.02        1888475.       13895325.
      1888175.02     13894925.03
#Sta/Elev= 30
  4557.1    1918  4593.2 1911.76  4622.8 1892.19    4662 1871.53  4703.9 1853.56
  4727.9 1845.93  4760.9 1842.55  4831.3  1841.5  4851.5    1836  4911.3 1829.16
  4929.9 1822.88  4955.4 1819.86  4960.8 1816.78  4961.3 1816.28  4973.6 1816.78
  5005.9 1817.54  5039.2 1822.37  5046.5 1821.66  5058.4 1822.64    5093 1835.08
  5135.4 1835.37  5245.9 1844.81    5273 1844.01    5333 1847.44  5362.2 1851.68
  5385.2 1858.91  5437.2 1880.98  5465.9 1895.98    5483 1901.17  5504.3 1903.24
#Mann= 7 ,-1 , 0
  4557.1      .1       0  4929.9     .07       0  4960.8     .05       0
  4973.6     .07       0  5046.5      .1       0  5135.4     .07       0
  5385.2      .1       0
Bank Sta=4960.8,4973.6
XS Rating Curve= 0 ,0
Exp/Cntr=0.3,0.1

Type RM Length L Ch R = 1 ,16391   ,584,584,584
BEGIN DESCRIPTION:
Bushwhack Creek 31.0
END DESCRIPTION:
XS GIS Cut Line= 3
      1888825.01     13895625.03       1888705.3     13895132.92
      1888524.99     13894424.98
#Sta/Elev= 30
  4503.4 1909.47  4541.8 1903.84  4557.2  1892.3  4597.9 1868.75  4622.1 1856.58
  4651.1  1846.5  4730.1 1840.32  4835.1 1840.24  4843.8 1838.46  4875.2 1823.97
  4895.9 1819.59  4912.9 1819.37  4958.6 1820.59  4976.9 1815.65  4977.4 1815.15
  4989.7 1815.65  5026.6  1819.3  5069.4 1818.69  5085.5 1824.06    5098 1830.58
  5118.7  1839.3  5144.2 1842.98  5175.2    1841  5266.3 1847.12  5357.8 1851.94
  5392.6 1853.91    5429 1859.65  5608.6 1914.29  5689.1 1941.46  5740.4 1954.93
#Mann= 9 ,-1 , 0
  4503.4      .1       0  4651.1     .07       0  4912.9      .1       0
  4976.9     .05       0  4989.7      .1       0  5085.5     .07       0
    5098      .1       0  5266.3     .07       0  5357.8      .1       0
Bank Sta=4976.9,4989.7
XS Rating Curve= 0 ,0
Exp/Cntr=0.3,0.1

Type RM Length L Ch R = 1 ,15807   ,357,357,357
BEGIN DESCRIPTION:
Bushwhack Creek 30.0
END DESCRIPTION:
XS GIS Cut Line= 3
        1889025.       13895375.        1889125.       13894775.
      1888624.97     13894324.97
#Sta/Elev= 30
  4391.7 1838.25  4461.9 1832.74  4641.3 1830.12  4679.6 1821.17  4720.4 1817.76
  4873.4 1816.34  4890.7 1814.89  4951.9 1815.53  4972.5 1812.36    4973 1811.86
  4985.4 1812.36  5003.6 1814.23  5024.9  1826.3  5040.7 1829.02  5065.2 1828.55
  5083.3 1823.72  5091.5 1826.64  5107.7 1831.43  5175.7 1831.13  5302.1 1836.61
  5328.6 1841.09    5390 1861.43  5470.7 1895.91  5525.1 1915.54  5556.4 1930.82
  5610.3 1953.32  5623.7 1960.57  5628.1 1965.95  5632.7 1968.55  5672.7 1971.15
#Mann= 8 ,-1 , 0
  4391.7     .07       0  4679.6    .035       0  4873.4     .07       0
  4951.9      .1       0  4972.5     .05       0  4985.4      .1       0
  5091.5     .07       0  5302.1      .1       0
Bank Sta=4972.5,4985.4
XS Rating Curve= 0 ,0
Exp/Cntr=0.3,0.1

Type RM Length L Ch R = 1 ,15450   ,581,581,581
BEGIN DESCRIPTION:
Bushwhack Creek 29.0
END DESCRIPTION:
XS GIS Cut Line= 4
      1889124.99     13895625.03      1889458.97     13894790.08
      1889434.75     13894557.31      1888924.98     13894174.99
#Sta/Elev= 30
  3985.3 1901.89  4099.8 1897.53  4132.1 1890.86  4187.7 1868.31  4232.3 1848.15
  4264.6 1836.04  4274.3 1835.65  4287.1 1831.77  4402.7 1828.74  4686.3 1827.43
  4760.6  1815.7  4790.3 1816.59  4886.5 1817.98  5010.3  1811.3  5012.7 1810.09
  5013.2 1809.59  5025.6 1810.09  5031.2 1811.12  5034.3 1825.18  5035.8 1829.62
  5040.3  1833.3  5129.3 1831.78  5334.5  1833.7  5498.5 1836.97  5517.9 1837.37
    5578 1841.65  5601.6 1847.97  5665.9 1879.75  5704.5 1901.35  5755.8  1925.6
#Mann= 11 ,-1 , 0
  3985.3      .1       0  4187.7     .07       0  4402.7    .035       0
  4790.3     .07       0  5010.3      .1       0  5012.7     .05       0
  5025.6      .1       0  5129.3     .07       0  5334.5    .035       0
  5498.5     .07       0  5517.9      .1       0
Bank Sta=5012.7,5025.6
XS Rating Curve= 0 ,0
Exp/Cntr=0.3,0.1

Type RM Length L Ch R = 1 ,14869   ,480,480,480
BEGIN DESCRIPTION:
Bushwhack Creek 28.0
END DESCRIPTION:
XS GIS Cut Line= 3
        1889375.       13895325.        1889975.       13894725.
      1890324.98     13894575.01
#Sta/Elev= 30
  4151.5 1827.71  4196.5 1826.63  4530.2 1823.32  4585.3 1824.55  4606.5 1821.99
  4674.4 1821.51  4703.4    1819  4712.6 1819.39  4728.2 1825.16  4759.3  1817.6
  4826.3 1815.61  4876.9 1814.82  4965.9 1814.39  4988.4  1808.3  5010.6 1806.78
  5011.1 1806.28  5023.7 1806.78    5040  1809.3  5066.1 1808.36  5089.4 1810.44
  5111.8 1809.42  5137.9 1824.02  5167.1 1851.82  5196.9 1874.75  5278.3 1921.87
  5288.9 1931.82  5338.6 1963.05  5346.8  1979.8  5354.6 1982.22  5380.8 1981.43
#Mann= 8 ,-1 , 0
  4151.5     .07       0  4196.5    .035       0  4826.3     .07       0
  4876.9    .035       0  4965.9     .07       0  5010.6     .05       0
  5023.7     .07       0  5089.4      .1       0
#XS Ineff= 2 , 0
         4731.47 1825.15
Permanent Ineff=
       F       F
Bank Sta=5010.6,5023.7
XS Rating Curve= 0 ,0
Exp/Cntr=0.3,0.1

Type RM Length L Ch R = 1 ,14389   ,385,385,385
BEGIN DESCRIPTION:
Bushwhack Creek 27.0
END DESCRIPTION:
XS GIS Cut Line= 3
      1889446.43     13895310.01      1890085.49     13895105.15
      1890429.87     13894888.41
#Sta/Elev= 30
  4339.9 1826.32  4553.7 1823.84  4582.2 1823.39  4653.2  1824.2  4672.1 1821.79
  4714.3 1820.11    4754 1820.74  4769.7 1819.14  4845.3    1819  4856.1 1818.47
  4864.3 1816.19    4896 1812.03  4968.2 1811.62  4993.4 1807.37  5011.2 1807.21
  5016.5 1805.52    5017 1805.02  5029.7 1805.52  5037.2 1806.84  5090.5 1806.89
  5104.8 1808.53  5115.3 1812.29  5125.9 1825.25  5147.2 1838.98  5206.2 1866.53
  5246.4 1887.62  5271.2 1899.31    5367 1934.92  5396.2 1941.79  5417.9 1945.44
#Mann= 7 ,-1 , 0
  4339.9    .035       0  4553.7      .1       0  4582.2     .07       0
  4714.3    .035       0    4896      .1       0  5016.5     .05       0
  5029.7      .1       0
#XS Ineff= 2 , 0
         4749.65 1824.59
Permanent Ineff=
       F       F
Bank Sta=5016.5,5029.7
XS Rating Curve= 0 ,0
Exp/Cntr=0.3,0.1

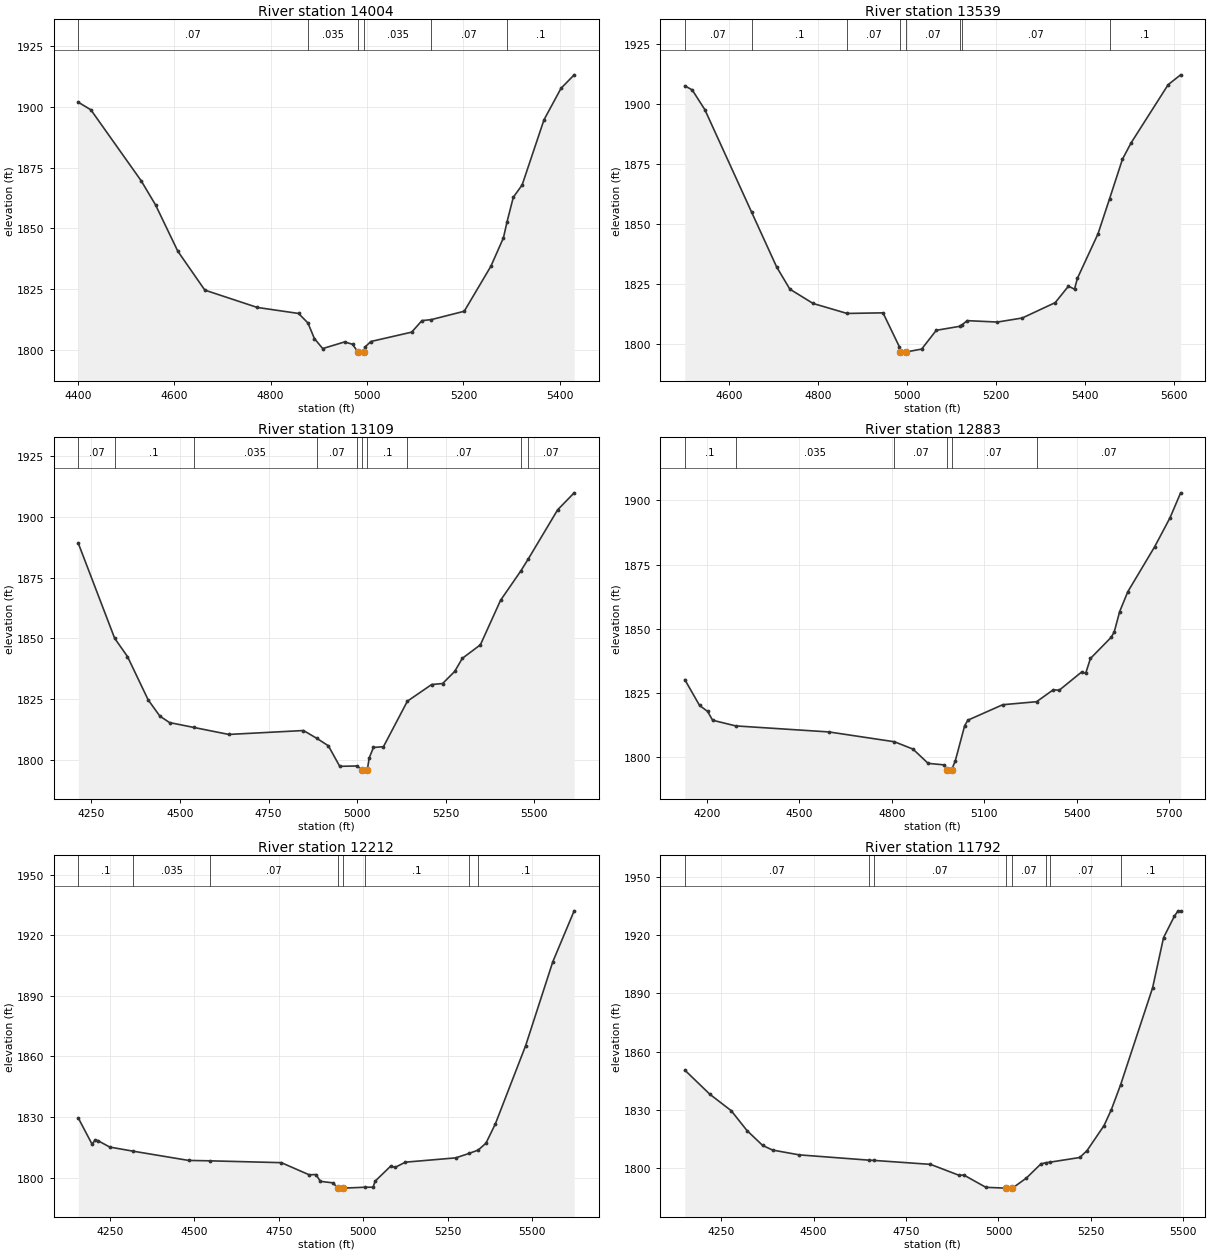
Type RM Length L Ch R = 1 ,14004   ,465,465,465
BEGIN DESCRIPTION:
Bushwhack Creek 26.0
END DESCRIPTION:
XS GIS Cut Line= 3
      1889924.98     13895975.04        1890175.       13895425.
      1890475.03     13895124.97
#Sta/Elev= 30
  4401.3 1901.91  4427.4 1898.77  4531.7 1869.57  4561.5 1859.64  4607.6 1840.61
  4663.7 1824.58  4772.4 1817.45  4858.1 1814.97  4877.5 1811.07    4891 1804.63
  4908.2 1800.52  4953.7 1803.25  4970.1 1802.28  4981.1 1799.14  4981.6 1798.64
  4994.9 1799.14  4995.2 1801.01    5008 1803.42  5092.8 1807.28    5114 1812.02
  5133.3 1812.43  5201.8 1815.88    5257 1834.38  5283.1  1846.1  5290.7 1852.78
  5303.6 1862.82  5321.9 1867.86  5367.3 1894.71  5402.5 1907.63  5429.8 1913.19
#Mann= 6 ,-1 , 0
  4401.3     .07       0  4877.5    .035       0  4981.1    .035       0
  4994.9    .035       0  5133.3     .07       0  5290.7      .1       0
Bank Sta=4981.1,4994.9
XS Rating Curve= 0 ,0
Exp/Cntr=0.3,0.1

Type RM Length L Ch R = 1 ,13539   ,430,430,430
BEGIN DESCRIPTION:
Bushwhack Creek 25.0
END DESCRIPTION:
XS GIS Cut Line= 3
        1890075.       13896125.        1890425.       13895775.
      1890574.99     13895175.05
#Sta/Elev= 30
  4501.1 1907.54  4517.7 1905.85  4546.1 1897.63  4651.4 1854.79  4707.3 1832.08
    4737 1822.82  4789.3 1816.84  4865.4 1812.69  4946.2 1812.94  4983.1 1798.74
  4984.7 1796.65  4985.2 1796.15  4998.5 1796.65    5033 1797.84  5065.8 1805.66
    5118 1807.31  5124.3 1808.04  5135.2 1809.69  5203.1  1809.1  5258.9 1810.79
  5332.9  1817.2  5362.7 1824.08  5376.2 1822.78  5382.6 1827.29  5428.8 1845.79
  5454.8  1860.4  5483.9 1876.98    5503 1883.69  5586.5 1908.03  5614.5 1912.13
#Mann= 8 ,-1 , 0
  4501.1     .07       0  4651.4      .1       0  4865.4     .07       0
  4984.7     .05       0  4998.5     .07       0    5118      .1       0
  5124.3     .07       0  5454.8      .1       0
Bank Sta=4984.7,4998.5
XS Rating Curve= 0 ,0
Exp/Cntr=0.3,0.1

Type RM Length L Ch R = 1 ,13109   ,226,226,226
BEGIN DESCRIPTION:
Bushwhack Creek 24.0
END DESCRIPTION:
XS GIS Cut Line= 3
      1890224.99     13896275.01        1890825.       13895775.
        1890675.       13895175.
#Sta/Elev= 30
    4213 1889.13  4315.5 1850.04  4351.7 1842.52  4410.1 1824.67  4443.1 1817.98
  4470.4 1815.32  4538.7 1813.32  4637.6 1810.43  4848.5 1812.04  4886.6 1808.78
  4918.8 1805.75  4950.8  1797.3  4998.7 1797.44  5014.8 1795.82  5015.3 1795.32
  5028.6 1795.82    5034 1800.75    5046 1805.07  5074.2 1805.38  5141.8 1824.13
  5210.3 1830.99  5241.2  1831.4  5275.2 1836.36  5296.9 1841.78  5347.8 1847.33
  5404.7 1865.66  5462.3 1877.85  5483.4  1882.8  5565.9 1902.94  5612.5 1909.93
#Mann= 10 ,-1 , 0
    4213     .07       0  4315.5      .1       0  4538.7    .035       0
  4886.6     .07       0  4998.7      .1       0  5014.8     .05       0
  5028.6      .1       0  5141.8     .07       0  5462.3      .1       0
  5483.4     .07       0
Bank Sta=5014.8,5028.6
XS Rating Curve= 0 ,0
Exp/Cntr=0.3,0.1

Type RM Length L Ch R = 1 ,12883   ,671,671,671
BEGIN DESCRIPTION:
Bushwhack Creek 23.0
END DESCRIPTION:
XS GIS Cut Line= 3
        1890575.     13896575.01      1891066.89     13895775.81
      1890740.38     13895191.61
#Sta/Elev= 30
  4128.9 1830.19  4176.6 1820.16  4202.7 1817.81  4219.1 1814.37  4293.7 1812.16
    4596 1809.81  4808.7 1805.98  4868.7 1803.13    4918 1797.56  4969.4 1796.98
  4980.2 1795.04  4980.7 1794.54    4994 1795.04    5006 1798.55  5036.4 1812.25
  5046.9  1814.4  5159.8 1820.41  5269.5 1821.58  5323.9 1826.25  5342.7 1826.03
  5416.1  1833.2  5428.7 1832.63  5444.2 1838.43  5511.4 1846.66  5521.3 1848.77
  5538.9 1856.67  5565.4 1864.44  5652.3 1881.93  5702.1  1893.2  5736.6 1902.95
#Mann= 6 ,-1 , 0
  4128.9      .1       0  4293.7    .035       0  4808.7     .07       0
  4980.2     .05       0    4994     .07       0  5269.5     .07       0
Bank Sta=4980.2,4994
XS Rating Curve= 0 ,0
Exp/Cntr=0.3,0.1

Type RM Length L Ch R = 1 ,12212   ,420,420,420
BEGIN DESCRIPTION:
Bushwhack Creek 22.0
END DESCRIPTION:
XS GIS Cut Line= 3
      1890775.01     13896974.99        1891375.       13896375.
      1891975.02       13896225.
#Sta/Elev= 30
  4156.5 1829.47  4197.1 1816.55  4205.6 1818.41  4214.1 1818.32  4249.6 1815.11
  4318.5 1813.08  4482.9  1808.5    4547  1808.3  4757.2 1807.39  4839.3  1801.4
  4859.7 1801.51  4872.5 1798.15  4909.9 1797.39  4924.5 1794.79    4925 1794.29
  4940.8 1794.79  5003.8 1795.22  5028.5 1795.25  5034.6 1798.23    5081 1805.73
  5093.4 1805.03  5124.3 1807.64  5272.8 1809.76    5312 1811.93  5339.7 1813.65
  5362.5 1817.02  5390.3 1826.57  5479.9  1865.3  5560.3 1906.86  5623.5 1932.08
#Mann= 8 ,-1 , 0
  4156.5      .1       0  4318.5    .035       0    4547     .07       0
  4924.5     .05       0  4940.8     .07       0  5003.8      .1       0
    5312     .07       0  5339.7      .1       0
Bank Sta=4924.5,4940.8
XS Rating Curve= 0 ,0
Exp/Cntr=0.3,0.1

Type RM Length L Ch R = 1 ,11792   ,430,430,430
BEGIN DESCRIPTION:
Bushwhack Creek 21.0
END DESCRIPTION:
XS GIS Cut Line= 3
      1890974.97     13897325.03        1891575.       13896725.
      1892024.99     13896525.01
#Sta/Elev= 30
  4151.6 1850.46  4219.2 1838.02  4277.2 1829.51  4319.7  1819.3  4362.1 1811.62
  4388.9 1809.22    4461 1806.74  4650.8 1803.99  4662.4 1803.89  4816.1 1801.84
  4893.1 1796.22  4906.5 1796.32  4965.9    1790  5021.2 1789.57  5021.7 1789.07
  5037.6 1789.57  5075.4 1794.77    5115 1802.13  5128.7 1802.69    5140 1802.99
  5219.9 1805.38  5239.6 1808.97  5285.5 1821.86  5305.2 1830.05  5330.2 1842.83
  5416.8 1892.87  5446.4 1918.76  5475.9 1929.89  5485.8 1932.58  5492.6 1932.54
#Mann= 8 ,-1 , 0
  4151.6     .07       0  4650.8    .035       0  4662.4     .07       0
  5021.2     .05       0  5037.6     .07       0  5128.7      .1       0
    5140     .07       0  5330.2      .1       0
Bank Sta=5021.2,5037.6
XS Rating Curve= 0 ,0
Exp/Cntr=0.3,0.1

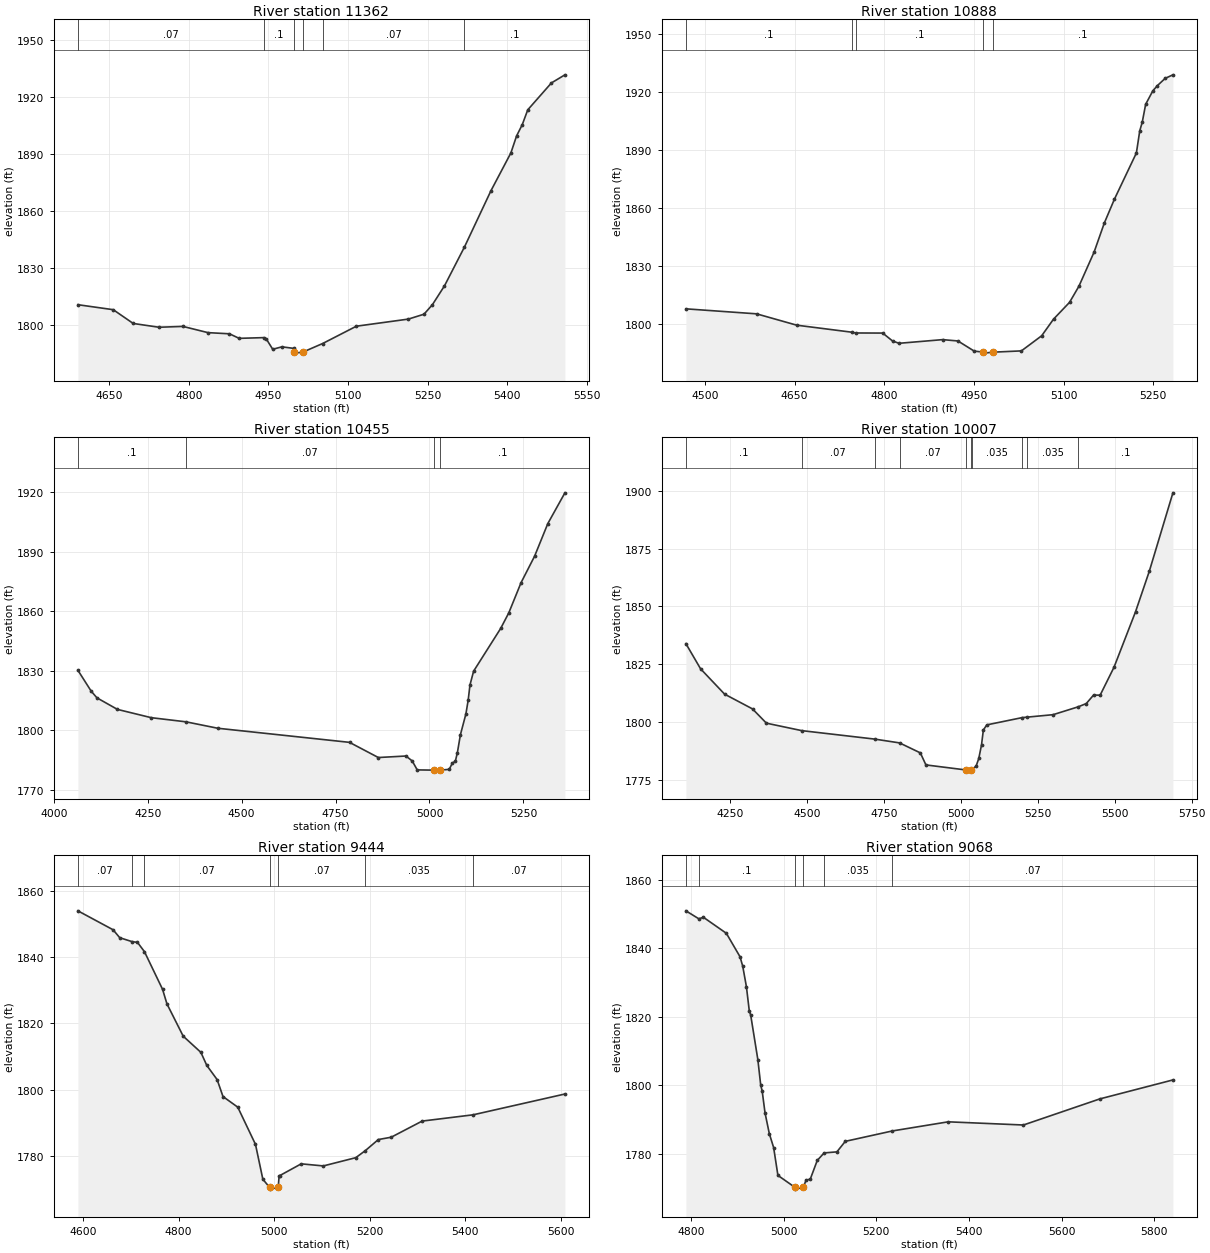
Type RM Length L Ch R = 1 ,11362   ,474,474,474
BEGIN DESCRIPTION:
Bushwhack Creek 20.0
END DESCRIPTION:
XS GIS Cut Line= 3
        1891625.     13897375.01        1891825.       13897025.
        1892075.       13896575.
#Sta/Elev= 30
    4591 1810.48  4657.6 1807.85  4695.3 1800.58  4743.9 1798.58  4788.9 1799.03
  4836.2 1795.74  4876.7 1795.13  4894.9 1792.73  4941.4 1793.11  4946.2 1792.36
  4958.2 1786.96  4975.5 1788.25  4997.7 1787.44  4998.2 1785.43  4998.7 1784.93
  5014.7 1785.43  5052.3    1790  5115.9 1799.14  5213.9 1802.89  5243.3 1805.47
  5259.3 1810.54  5281.9 1820.42  5319.5 1840.88  5369.6 1870.68  5407.1 1890.59
  5417.8 1899.53  5428.6 1905.55  5438.9 1913.32  5483.5 1927.51  5508.9 1931.78
#Mann= 6 ,-1 , 0
    4591     .07       0  4941.4      .1       0  4998.2     .05       0
  5014.7      .1       0  5052.3     .07       0  5319.5      .1       0
Bank Sta=4998.2,5014.7
XS Rating Curve= 0 ,0
Exp/Cntr=0.3,0.1

Type RM Length L Ch R = 1 ,10888   ,433,433,433
BEGIN DESCRIPTION:
Bushwhack Creek 19.0
END DESCRIPTION:
XS GIS Cut Line= 3
      1891737.23     13897627.34        1892175.       13897325.
      1892375.02     13897124.98
#Sta/Elev= 30
    4468 1807.87  4586.2 1805.29  4653.4 1799.43  4745.6  1795.8  4752.2  1795.4
  4797.3 1795.35  4813.8 1791.26  4824.7 1790.07  4897.6 1791.96  4923.2 1791.27
  4950.4 1786.04  4965.9 1785.49  4966.4 1784.99  4982.5 1785.49  5029.4 1786.15
  5063.3 1793.95  5083.2 1802.56    5110 1811.24  5125.6 1819.52  5151.1 1837.24
  5168.1 1852.17    5185 1864.49  5221.8 1888.39  5227.4 1899.77  5231.7 1904.43
  5237.3 1913.52  5249.3 1920.48  5257.1 1923.22  5269.9 1926.91  5282.9 1928.75
#Mann= 5 ,-1 , 0
    4468      .1       0  4745.6     .07       0  4752.2      .1       0
  4965.9     .05       0  4982.5      .1       0
Bank Sta=4965.9,4982.5
XS Rating Curve= 0 ,0
Exp/Cntr=0.3,0.1

Type RM Length L Ch R = 1 ,10455   ,448,448,448
BEGIN DESCRIPTION:
Bushwhack Creek 18.0
END DESCRIPTION:
XS GIS Cut Line= 3
      1891534.16     13898035.44        1892375.       13897625.
      1892574.99     13897325.02
#Sta/Elev= 30
  4064.3 1830.28  4099.5 1819.81    4115 1816.39  4169.6 1810.57  4259.7  1806.4
  4351.9 1804.32  4436.6 1801.08  4787.2 1793.98  4863.9 1786.34  4937.4  1787.1
  4954.1 1784.62  4967.4 1780.11  5011.9 1779.99  5012.4 1779.49  5028.5 1779.99
  5052.6 1780.38  5060.8 1783.48  5068.9 1784.49  5074.3 1788.79  5082.4 1797.84
    5097 1808.31  5103.1 1815.29  5107.8 1822.87  5117.5 1829.83  5189.6 1851.37
  5211.3 1859.26  5243.7 1874.36  5279.8 1887.72    5315 1904.15  5360.5 1919.63
#Mann= 4 ,-1 , 0
  4064.3      .1       0  4351.9     .07       0  5011.9     .05       0
  5028.5      .1       0
Bank Sta=5011.9,5028.5
XS Rating Curve= 0 ,0
Exp/Cntr=0.3,0.1

Type RM Length L Ch R = 1 ,10007   ,563,563,563
BEGIN DESCRIPTION:
Bushwhack Creek 17.0
END DESCRIPTION:
XS GIS Cut Line= 3
      1891641.25     13898105.35        1892525.       13898025.
      1892874.99     13897425.02
#Sta/Elev= 30
  4107.1  1833.9  4154.8 1822.99  4232.9 1812.01  4323.5 1805.62  4368.7 1799.44
  4483.5 1796.21  4720.1 1792.55  4801.1  1790.9  4868.7 1786.57  4886.8 1781.36
  5017.2 1779.17  5017.7 1778.67  5033.8 1779.17  5035.5 1779.42  5049.6 1780.75
  5058.5 1784.15  5067.4 1790.03  5073.4  1796.5  5084.6  1798.7  5199.4 1801.85
  5215.1 1802.05  5299.9 1803.12  5381.8 1806.54  5407.6 1807.93  5431.4 1811.62
  5452.7 1811.56  5497.9  1823.7  5567.6 1847.66  5612.5 1865.27  5689.1 1899.21
#Mann= 10 ,-1 , 0
  4107.1      .1       0  4483.5     .07       0  4720.1    .035       0
  4801.1     .07       0  5017.2     .05       0  5033.8     .07       0
  5035.5    .035       0  5199.4     .07       0  5215.1    .035       0
  5381.8      .1       0
Bank Sta=5017.2,5033.8
XS Rating Curve= 0 ,0
Exp/Cntr=0.3,0.1

Type RM Length L Ch R = 1 ,9444    ,376,376,376
BEGIN DESCRIPTION:
Mapping XS d4f51b44
END DESCRIPTION:
XS GIS Cut Line= 2
      1892544.37     13898941.35      1892785.09     13897950.88
#Sta/Elev= 30
  4589.1 1853.98  4662.7 1848.27  4676.7 1845.87  4702.1  1844.7  4713.8 1844.46
  4728.4 1841.66  4766.3  1830.3  4775.5  1825.9  4809.5 1816.16  4846.5 1811.28
  4858.9 1807.33  4880.5 1803.06  4892.8 1797.94  4923.7 1794.74  4960.8 1783.51
  4976.2 1772.99  4990.5 1770.51    4991 1770.01  5008.3 1770.51  5010.2 1773.84
  5011.6 1774.09  5056.5 1777.64  5102.8 1777.01  5170.7  1779.5  5190.8 1781.64
  5217.9 1784.97  5244.8 1785.67  5309.6 1790.54  5416.2 1792.43  5608.4 1798.71
#Mann= 7 ,-1 , 0
  4589.1     .07       0  4702.1    .063       0  4728.4     .07       0
  4990.5     .05       0  5008.3     .07       0  5190.8    .035       0
  5416.2     .07       0
Bank Sta=4990.5,5008.3
XS Rating Curve= 0 ,0
Exp/Cntr=0.3,0.1

Type RM Length L Ch R = 1 ,9068    ,454,454,454
BEGIN DESCRIPTION:
Bushwhack Creek 16.0
END DESCRIPTION:
XS GIS Cut Line= 3
        1892925.     13898874.99        1892975.       13898675.
      1892859.68     13897837.45
#Sta/Elev= 30
  4788.9 1850.94  4816.9 1848.61  4826.8 1849.05  4876.3 1844.38  4905.8 1837.53
  4911.6  1834.8  4919.6 1828.79  4925.8 1821.73  4928.9 1820.46  4944.3 1807.49
  4950.5 1800.03  4953.6 1798.37  4959.8 1791.94  4969.1 1785.86  4978.4 1781.81
  4987.6  1773.7  5024.6 1770.19  5025.1 1769.69  5042.4 1770.19  5048.4 1772.33
  5057.4 1772.58  5072.6 1778.08  5087.4 1780.26    5115 1780.57  5133.1 1783.64
  5234.9 1786.68  5355.3 1789.34  5517.7 1788.41  5682.7 1796.03  5840.5 1801.57
#Mann= 6 ,-1 , 0
  4788.9     .07       0  4816.9      .1       0  5024.6     .05       0
  5042.4      .1       0  5087.4    .035       0  5234.9     .07       0
Bank Sta=5024.6,5042.4
XS Rating Curve= 0 ,0
Exp/Cntr=0.3,0.1

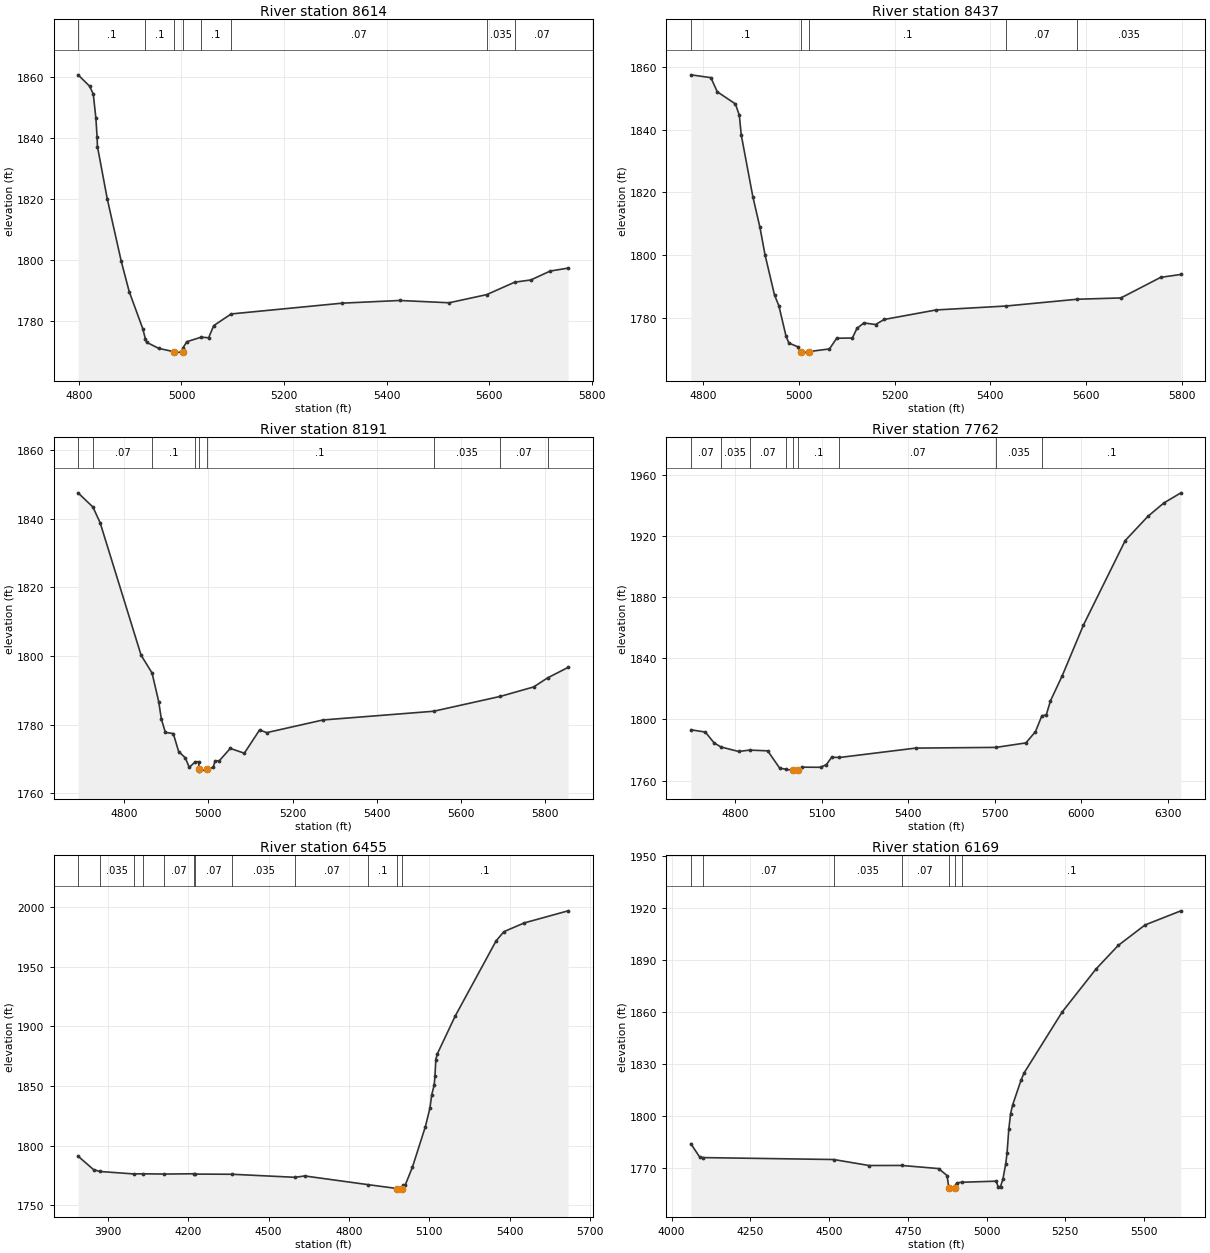
Type RM Length L Ch R = 1 ,8614    ,177,177,177
BEGIN DESCRIPTION:
Bushwhack Creek 15.0
END DESCRIPTION:
XS GIS Cut Line= 3
        1893425.     13898724.99        1893375.       13898525.
      1892925.03     13897925.04
#Sta/Elev= 30
  4798.2 1860.71  4820.7 1857.01  4827.9 1854.42    4833 1846.55  4835.3 1840.51
  4836.1 1837.21  4855.1 1820.17  4882.5 1799.66    4898 1789.73  4924.4 1777.62
  4929.8 1774.11  4931.8 1773.15  4955.9 1771.11  4984.7 1770.08  4985.2 1769.58
  5002.6 1770.08  5003.1 1771.33  5010.4 1773.32  5038.5 1774.81    5053 1774.61
  5062.9 1778.59    5097 1782.41  5314.1 1785.95  5425.8 1786.82  5522.2 1786.07
  5595.3 1788.73  5650.3 1792.82  5681.6 1793.54  5719.4 1796.46  5754.3 1797.42
#Mann= 8 ,-1 , 0
  4798.2      .1       0  4929.8      .1       0  4984.7     .05       0
  5002.6      .1       0  5038.5      .1       0    5097     .07       0
  5595.3    .035       0  5650.3     .07       0
Bank Sta=4984.7,5002.6
XS Rating Curve= 0 ,0
Exp/Cntr=0.3,0.1

Type RM Length L Ch R = 1 ,8437    ,246,246,246
BEGIN DESCRIPTION:
Mapping XS 23d1b15c
END DESCRIPTION:
XS GIS Cut Line= 3
       1893554.4     13898741.81      1893504.38      13898342.8
      1893062.75     13897903.71
#Sta/Elev= 30
  4773.7 1857.43  4815.6 1856.53    4829 1852.03    4867 1848.16  4875.1 1844.53
  4879.1 1838.33  4903.3 1818.69  4918.1 1808.97  4928.9 1800.13  4948.7 1787.36
  4957.8 1783.95  4972.9 1774.18  4978.9 1772.07  4997.1 1770.92  5003.2 1769.38
  5003.7 1768.88  5021.1 1769.38  5063.6 1770.22  5078.7 1773.62  5111.6 1773.69
    5121 1776.74  5135.7  1778.5  5159.9 1777.98  5178.1 1779.59  5286.7 1782.62
  5432.9 1783.87  5581.9 1786.03  5673.1 1786.44  5756.3 1792.99  5798.6 1793.92
#Mann= 5 ,-1 , 0
  4773.7      .1       0  5003.2     .05       0  5021.1      .1       0
  5432.9     .07       0  5581.9    .035       0
Bank Sta=5003.2,5021.1
XS Rating Curve= 0 ,0
Exp/Cntr=0.3,0.1

Type RM Length L Ch R = 1 ,8191    ,429,429,429
BEGIN DESCRIPTION:
Bushwhack Creek 14.0
END DESCRIPTION:
XS GIS Cut Line= 3
        1893625.     13898675.01        1893725.       13898375.
      1893124.98     13897774.98
#Sta/Elev= 30
  4690.1 1847.52  4725.5 1843.38  4742.6  1838.8    4840 1800.19    4866 1795.02
  4881.8 1786.69  4888.1  1781.6  4897.6 1777.72  4916.5 1777.36  4929.2 1772.13
    4945  1770.3  4954.5 1767.51  4968.6 1769.15  4976.6 1769.15  4978.1 1766.92
  4978.6 1766.42    4996 1766.92  5011.3  1767.5  5015.6 1769.33  5026.2 1769.49
  5051.9 1773.05  5085.3 1771.64  5121.6 1778.42  5138.6 1777.64  5272.3 1781.33
  5535.3 1783.87  5693.8  1788.2  5773.2 1790.96  5806.2  1793.6  5854.9 1796.65
#Mann= 9 ,-1 , 0
  4690.1      .1       0  4725.5     .07       0    4866      .1       0
  4968.6      .1       0  4978.1     .05       0    4996      .1       0
  5535.3    .035       0  5693.8     .07       0  5806.2    .035       0
Bank Sta=4978.1,4996
XS Rating Curve= 0 ,0
Exp/Cntr=0.3,0.1

Type RM Length L Ch R = 1 ,7762    ,1307,1307,1307
BEGIN DESCRIPTION:
Bushwhack Creek 13.0
END DESCRIPTION:
XS GIS Cut Line= 3
        1894025.       13898525.        1894075.       13898175.
      1893075.01     13897275.01
#Sta/Elev= 30
  4646.8 1793.19  4697.1  1791.7  4727.4 1784.62  4751.6 1781.94  4812.3 1779.01
  4850.5 1779.91  4913.2 1779.44  4954.7 1768.14  4977.5 1767.35  5000.7 1766.67
  5001.2 1766.17  5018.6 1766.67  5030.8 1768.77  5096.7 1768.68  5116.7 1770.45
  5135.2  1775.3    5162 1775.08  5425.8 1781.22    5705 1781.69  5808.3 1784.62
  5841.5 1791.97  5863.6 1802.34    5879 1802.96  5893.3 1812.04  5934.4 1828.58
    6008 1861.72  6152.6 1916.86  6231.1 1932.66  6286.3  1941.4  6345.7 1948.06
#Mann= 9 ,-1 , 0
  4646.8     .07       0  4751.6    .035       0  4850.5     .07       0
  4977.5      .1       0  5000.7     .05       0  5018.6      .1       0
    5162     .07       0    5705    .035       0  5863.6      .1       0
Bank Sta=5000.7,5018.6
XS Rating Curve= 0 ,0
Exp/Cntr=0.3,0.1

Type RM Length L Ch R = 1 ,6455    ,286,286,286
BEGIN DESCRIPTION:
Bushwhack Creek 12.1
END DESCRIPTION:
XS GIS Cut Line= 4
       1894053.3     13898479.89      1894165.24     13898371.14
      1894849.27     13897986.12      1895737.19     13897938.54
#Sta/Elev= 30
  3788.6  1791.3  3846.4 1780.01  3869.5 1778.45  3995.8  1776.4    4030 1776.49
    4111 1776.29  4219.8 1776.52  4226.2 1776.25  4363.8 1776.11  4599.4 1773.55
  4634.9  1774.7  4872.1 1767.39  4980.3 1764.15  4980.8 1763.65  4998.6 1764.15
  5001.1  1766.7  5010.6 1767.11  5037.5 1782.15  5085.6 1815.91  5102.7 1831.54
  5109.6 1842.86  5118.6 1850.89  5121.6 1858.52  5124.7  1872.1  5130.2 1876.95
  5196.8 1908.56  5349.7 1971.63  5378.8  1979.4  5455.1 1986.75  5618.8 1996.88
#Mann= 12 ,-1 , 0
  3788.6     .07       0  3869.5    .035       0  3995.8     .07       0
    4030    .035       0    4111     .07       0  4219.8    .035       0
  4226.2     .07       0  4363.8    .035       0  4599.4     .07       0
  4872.1      .1       0  4980.3     .05       0  4998.6      .1       0
Bank Sta=4980.3,4998.6
XS Rating Curve= 0 ,0
Exp/Cntr=0.3,0.1

Type RM Length L Ch R = 1 ,6169    ,233,233,233
BEGIN DESCRIPTION:
Bushwhack Creek 12.5
END DESCRIPTION:
XS GIS Cut Line= 5
      1894198.33     13898401.19      1894732.22     13898210.21
      1894964.42     13898208.04      1895116.33     13898205.87
      1895682.78     13898310.04
#Sta/Elev= 30
 4061.14 1784.19  4090.1 1776.25  4100.6 1776.18  4514.6 1775.07    4627 1771.61
  4730.5 1771.65  4847.7 1769.85  4874.7 1765.82  4880.5 1758.49    4881 1757.99
  4898.8 1758.49  4901.7 1760.57  4907.7 1761.63  4921.4 1761.96  5030.7 1762.58
  5036.7 1759.47  5044.5 1759.46  5052.2 1764.01    5061 1772.65  5065.1 1778.73
  5070.7 1792.48  5076.3 1801.47  5083.1 1806.67  5109.8 1820.97    5119 1824.95
  5240.3 1860.21  5347.7 1884.99  5418.1 1898.56  5503.3 1910.38  5617.2 1918.53
#Mann= 7 ,-1 , 0
 4061.14    .035       0  4100.6     .07       0  4514.6    .035       0
  4730.5     .07       0  4880.5     .05       0  4898.8     .07       0
  4921.4      .1       0
Bank Sta=4880.5,4898.8
XS Rating Curve= 0 ,0
Exp/Cntr=0.3,0.1

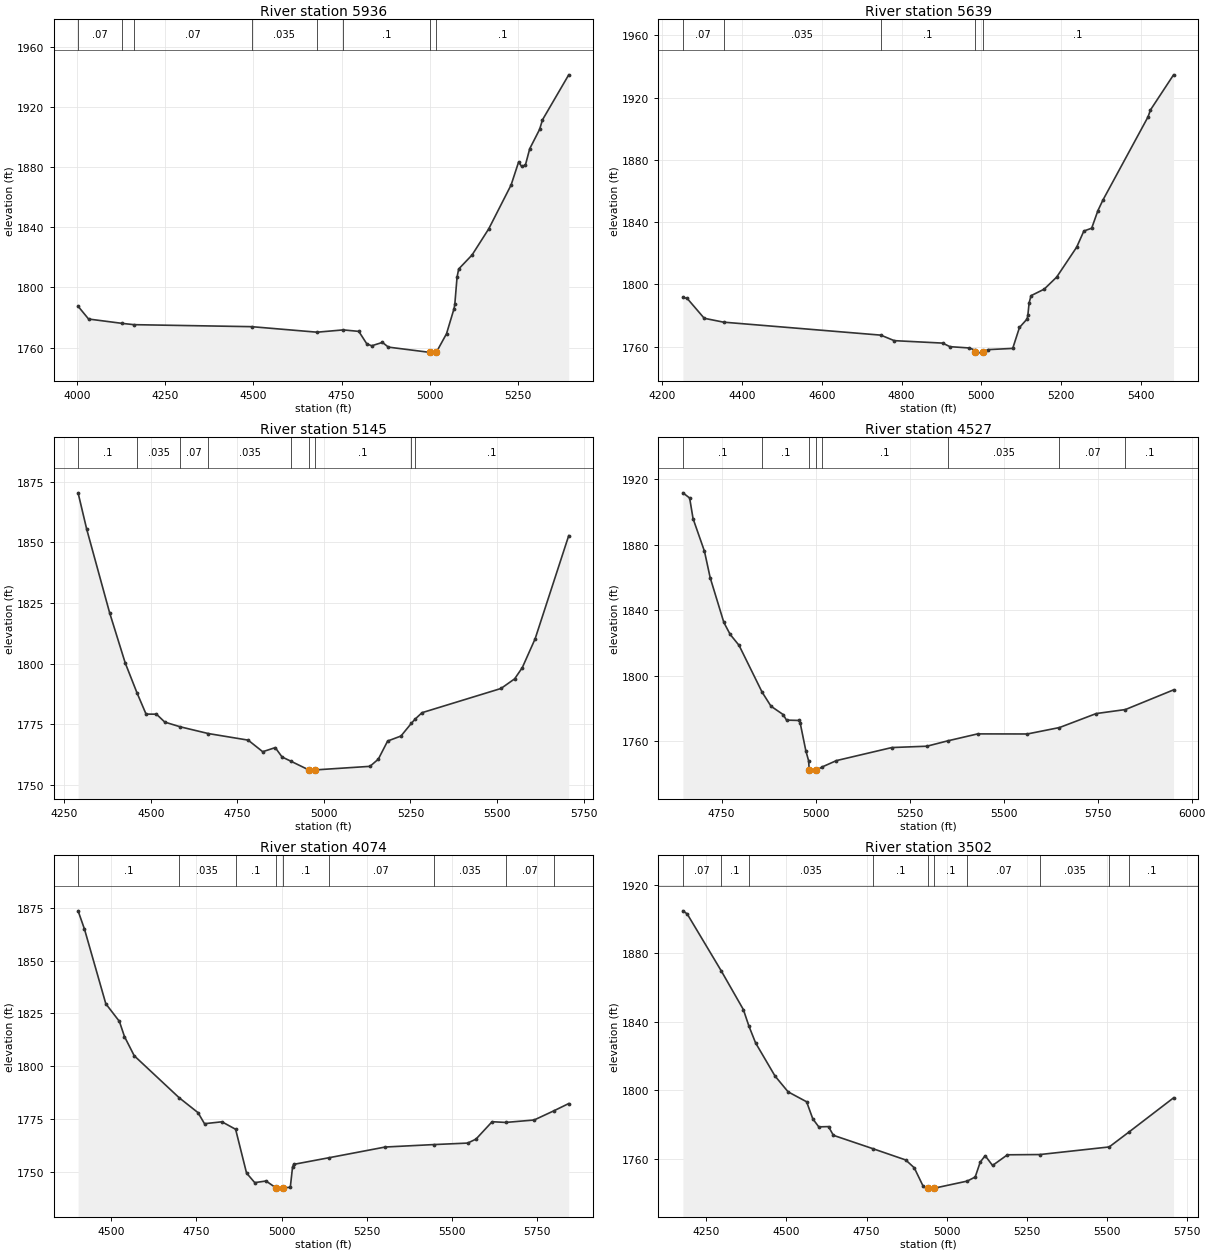
Type RM Length L Ch R = 1 ,5936    ,297,297,297
BEGIN DESCRIPTION:
Bushwhack Creek 12.0
END DESCRIPTION:
XS GIS Cut Line= 4
      1894083.96     13898471.24      1894740.75     13898282.88
        1895025.       13898425.      1895325.02     13898675.02
#Sta/Elev= 30
  4002.8  1787.5  4032.6 1779.01  4128.1 1776.11  4161.3 1775.26    4495 1773.93
  4680.6 1770.26  4754.9 1771.78    4799  1770.8    4822 1762.41  4835.9 1761.25
  4866.1 1763.48  4882.8 1760.35  5000.3 1756.85  5000.8 1756.35  5018.7 1756.85
  5047.8 1769.23  5069.1 1785.88  5071.3 1788.73  5077.7 1806.86  5082.3 1812.24
  5120.3 1821.58  5167.6 1838.95    5231 1868.09  5252.3 1883.36  5260.8  1880.4
  5271.5 1881.28  5283.8 1892.17  5311.9 1905.04  5319.9 1911.33  5394.4 1941.26
#Mann= 8 ,-1 , 0
  4002.8     .07       0  4128.1    .035       0  4161.3     .07       0
    4495    .035       0  4680.6     .07       0  4754.9      .1       0
  5000.3     .05       0  5018.7      .1       0
Bank Sta=5000.3,5018.7
XS Rating Curve= 0 ,0
Exp/Cntr=0.3,0.1

Type RM Length L Ch R = 1 ,5639    ,494,494,494
BEGIN DESCRIPTION:
Bushwhack Creek 11.0
END DESCRIPTION:
XS GIS Cut Line= 3
      1894074.95     13898524.99      1894797.52     13898630.82
      1895275.05     13898775.01
#Sta/Elev= 30
  4252.3 1791.71  4263.2 1790.98  4305.7 1778.27    4354 1775.78    4748 1767.44
  4781.7  1763.9    4903 1762.32  4921.2 1760.03  4969.7 1759.19  4984.7 1757.75
    4985 1756.38  4985.5 1755.88  5003.4 1756.38  5016.8 1758.13  5078.5 1758.91
  5095.4 1772.36  5114.6 1777.84  5116.5 1780.44  5119.5 1788.01  5124.3 1792.78
  5157.3 1796.97  5188.6 1804.73  5238.7 1823.95  5256.7 1834.32  5276.3 1836.14
    5292  1847.5  5304.6 1854.29  5417.4 1907.63  5423.6 1912.13  5481.4 1934.67
#Mann= 5 ,-1 , 0
  4252.3     .07       0    4354    .035       0    4748      .1       0
    4985     .05       0  5003.4      .1       0
Bank Sta=4985,5003.4
XS Rating Curve= 0 ,0
Exp/Cntr=0.3,0.1

Type RM Length L Ch R = 1 ,5145    ,618,618,618
BEGIN DESCRIPTION:
Bushwhack Creek 10.0
END DESCRIPTION:
XS GIS Cut Line= 3
      1893724.99       13898975.      1894435.47     13898916.81
      1895139.17       13898955.
#Sta/Elev= 30
  4289.6 1870.34  4314.4 1855.45  4380.7    1821  4425.8 1800.32  4459.6 1788.09
    4486 1779.26  4516.1 1779.22  4540.2 1775.96  4584.9 1774.02  4665.8 1771.25
    4781 1768.54  4823.1 1763.77  4859.3 1765.46    4879  1761.6  4904.4 1759.87
  4956.1 1756.28  4956.6 1755.78  4974.5 1756.28  5132.9 1757.75    5157 1760.69
    5184 1768.17  5222.5 1770.23  5252.2  1775.4  5262.5 1777.07  5283.2 1779.83
  5511.5  1789.8  5550.9 1793.76    5573 1798.37  5610.1 1810.24  5707.2 1852.72
#Mann= 9 ,-1 , 0
  4289.6      .1       0  4459.6    .035       0  4584.9     .07       0
  4665.8    .035       0  4904.4      .1       0  4956.1     .05       0
  4974.5      .1       0  5252.2     .07       0  5262.5      .1       0
Bank Sta=4956.1,4974.5
XS Rating Curve= 0 ,0
Exp/Cntr=0.3,0.1

Type RM Length L Ch R = 1 ,4527    ,453,453,453
BEGIN DESCRIPTION:
Bushwhack Creek 9.0
END DESCRIPTION:
XS GIS Cut Line= 3
      1893675.03       13899275.        1894025.       13899325.
      1894975.14     13899282.89
#Sta/Elev= 30
  4647.3 1911.81  4665.2 1908.65  4674.3 1896.05  4704.6 1876.14  4719.8    1860
  4756.1  1832.7  4772.9 1825.37  4796.6 1818.66  4857.7 1790.16  4881.5  1781.5
  4913.7 1776.42  4922.8 1773.01  4956.1 1772.79  4959.2 1771.19  4974.3 1754.14
  4981.5 1748.25  4983.3 1742.35  4983.8 1741.85  5001.7 1742.35  5018.4 1744.49
  5055.6 1748.29  5202.8 1756.25  5296.1 1757.07  5352.2 1760.38    5431 1764.59
  5563.1 1764.54  5648.6 1768.47  5746.3 1777.01  5823.9 1779.46  5951.9 1791.47
#Mann= 8 ,-1 , 0
  4647.3      .1       0  4857.7      .1       0  4983.3     .05       0
  5001.7      .1       0  5018.4      .1       0  5352.2    .035       0
  5648.6     .07       0  5823.9      .1       0
Bank Sta=4983.3,5001.7
XS Rating Curve= 0 ,0
Exp/Cntr=0.3,0.1

Type RM Length L Ch R = 1 ,4074    ,572,572,572
BEGIN DESCRIPTION:
Bushwhack Creek 8.0
END DESCRIPTION:
XS GIS Cut Line= 3
      1893575.01       13899675.        1894175.       13899725.
      1894933.09     13899368.49
#Sta/Elev= 30
  4402.6 1873.52  4421.4 1864.87    4484  1829.6  4523.8 1821.28  4538.8 1814.09
  4567.4 1805.03  4699.3 1785.18  4754.6 1778.14  4773.6 1772.92  4824.8 1773.82
  4864.9 1770.28    4897 1749.59  4921.1 1745.07  4954.2 1745.84  4984.2  1742.5
  4984.7    1742  5002.6  1742.5  5025.4  1742.9    5032 1752.46  5035.3  1753.7
  5138.3 1756.82  5303.9  1761.9    5446 1763.05  5545.9 1763.76  5570.3 1765.64
  5617.6 1773.86  5657.6 1773.52  5740.9 1774.67  5798.1 1778.96  5842.4 1782.44
#Mann= 9 ,-1 , 0
  4402.6      .1       0  4699.3    .035       0  4864.9      .1       0
  4984.2     .05       0  5002.6      .1       0  5138.3     .07       0
    5446    .035       0  5657.6     .07       0  5798.1      .1       0
Bank Sta=4984.2,5002.6
XS Rating Curve= 0 ,0
Exp/Cntr=0.3,0.1

Type RM Length L Ch R = 1 ,3502    ,559,559,559
BEGIN DESCRIPTION:
Bushwhack Creek 7.0
END DESCRIPTION:
XS GIS Cut Line= 3
      1894075.01     13900574.99       1894565.6     13899940.37
      1895024.99     13899375.01
#Sta/Elev= 30
  4177.1 1904.84  4190.4 1903.05  4296.2 1869.91  4365.8 1847.09  4382.8 1837.58
  4403.8 1827.65  4464.4 1808.29  4505.3 1799.03    4563 1793.23  4582.3 1783.25
  4600.9 1778.57  4631.3 1778.72  4646.5 1773.63  4769.6 1765.82  4872.2 1759.21
  4898.8 1754.64  4926.1 1744.04  4941.3 1742.67  4941.8 1742.17    4960 1742.67
  5063.9 1746.86  5088.9 1749.25  5104.5 1757.91  5119.9 1761.72  5143.1    1756
  5189.5 1762.24  5290.5 1762.38    5507 1766.83  5568.6 1775.55  5707.7 1795.53
#Mann= 10 ,-1 , 0
  4177.1     .07       0  4296.2      .1       0  4382.8    .035       0
  4769.6      .1       0  4941.3     .05       0    4960      .1       0
  5063.9     .07       0  5290.5    .035       0    5507     .07       0
  5568.6      .1       0
Bank Sta=4941.3,4960
XS Rating Curve= 0 ,0
Exp/Cntr=0.3,0.1