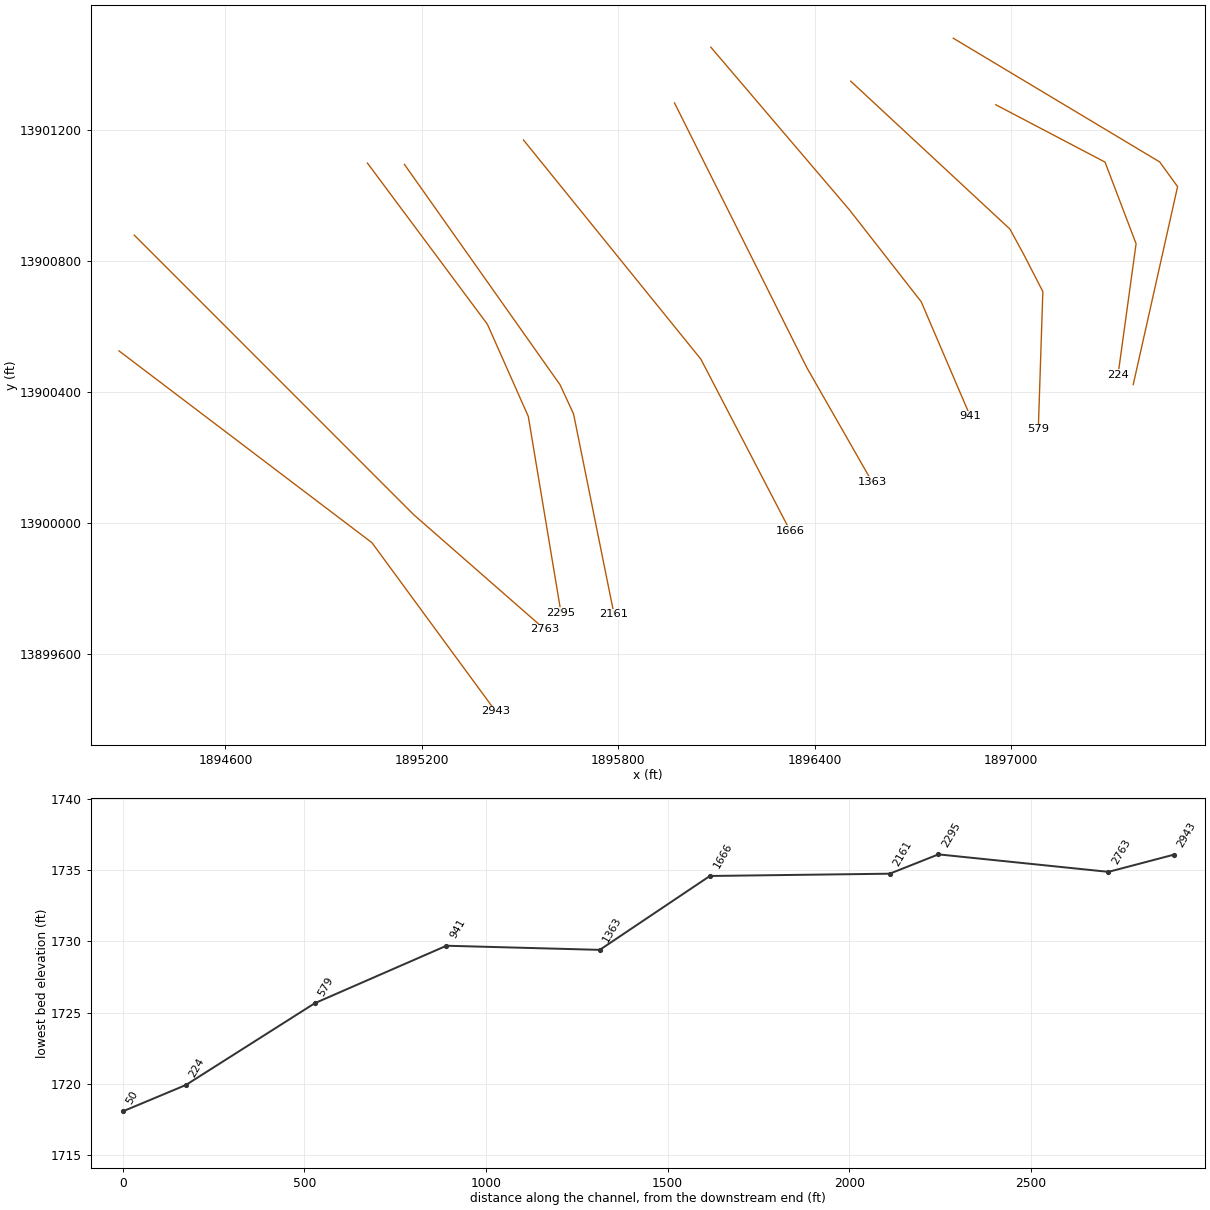
HEC-RAS study Bushwhack Creek.prj: Bushwhack Creek Base Level Engineering

--- Bushwhack Creek.g01 (geometry) --- (continued)

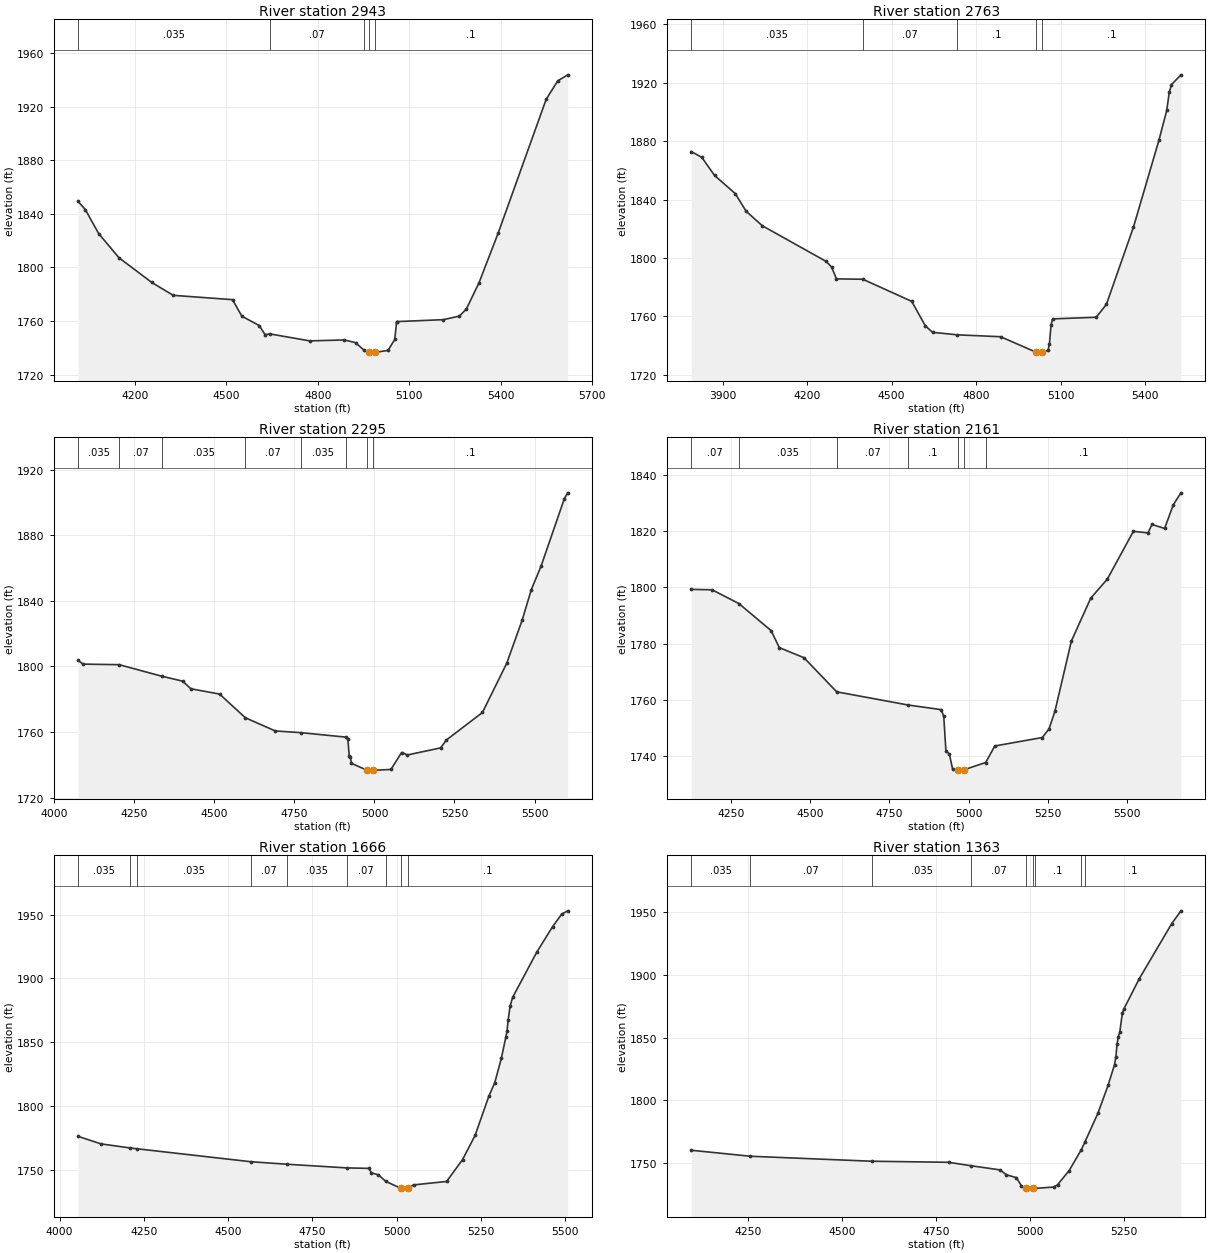
Type RM Length L Ch R = 1 ,2943    ,180,180,180
BEGIN DESCRIPTION:
Bushwhack Creek 6.0
END DESCRIPTION:
XS GIS Cut Line= 3
        1894275.       13900525.      1895047.59     13899939.31
      1895424.99     13899425.02
#Sta/Elev= 30
  4012.8 1849.39  4036.7 1843.21  4080.7 1825.27  4147.4 1807.21  4255.1 1788.82
  4325.4 1779.23  4519.9    1776  4550.6 1763.67  4607.8 1756.67  4626.6 1749.95
  4643.7 1750.41  4773.4 1745.24  4887.4 1745.95    4924  1743.9  4951.3 1738.35
  4967.4 1736.61  4967.9 1736.11  4986.1 1736.61  5030.4 1738.15  5052.6 1746.31
  5058.3 1759.03    5060 1759.64  5212.4 1761.08  5264.4 1763.73  5287.6 1769.01
  5329.1 1788.58  5391.8 1825.52  5549.8 1925.61  5587.7 1939.25  5620.2 1943.75
#Mann= 5 ,-1 , 0
  4012.8    .035       0  4643.7     .07       0  4951.3      .1       0
  4967.4     .05       0  4986.1      .1       0
Bank Sta=4967.4,4986.1
XS Rating Curve= 0 ,0
Exp/Cntr=0.3,0.1

Type RM Length L Ch R = 1 ,2763    ,468,468,468
BEGIN DESCRIPTION:
Bushwhack Creek 5.0
END DESCRIPTION:
XS GIS Cut Line= 4
       1894321.8      13900878.2        1894575.       13900625.
        1895175.       13900025.      1895574.99     13899675.01
#Sta/Elev= 30
  3788.7 1872.89  3826.2 1868.88  3871.2 1856.56    3945 1844.07  3983.2 1832.05
  4040.9 1822.09  4267.5 1797.68    4287  1793.8  4303.9 1785.73  4397.6 1785.47
  4571.2 1770.33  4619.6 1753.56  4645.1 1749.16  4733.4 1747.42  4886.9 1746.13
    5014  1735.4  5014.5  1734.9  5032.7  1735.4  5055.3 1736.87  5060.1 1741.41
  5065.7 1754.03  5071.2 1758.33    5226 1759.45  5262.1 1768.21    5358 1820.97
  5449.1  1880.9  5476.4 1901.04  5485.3 1913.35  5493.3 1918.72  5526.8  1925.4
#Mann= 5 ,-1 , 0
  3788.7    .035       0  4397.6     .07       0  4733.4      .1       0
    5014     .05       0  5032.7      .1       0
Bank Sta=5014,5032.7
XS Rating Curve= 0 ,0
Exp/Cntr=0.3,0.1

Type RM Length L Ch R = 1 ,2295    ,134,134,134
BEGIN DESCRIPTION:
Bushwhack Creek 4.0
END DESCRIPTION:
XS GIS Cut Line= 4
      1895033.69      13901098.4      1895400.22     13900606.13
        1895525.       13900325.        1895625.     13899724.99
#Sta/Elev= 30
    4074 1803.78  4089.8 1801.44  4202.5 1801.09  4335.9 1794.04  4400.7 1791.05
  4426.4 1786.39  4516.3 1783.15  4596.9 1768.67  4690.3 1760.65  4769.3 1759.62
  4910.4 1756.89  4916.8 1755.93  4921.3  1745.2  4924.6    1745  4927.9 1740.88
  4977.5 1736.63    4978 1736.13  4996.3 1736.63  5051.4 1737.16  5084.9 1747.49
  5103.1    1746  5206.5  1750.3  5224.8 1755.14  5337.3 1771.91  5413.3    1802
    5462 1828.59  5489.9 1846.86  5520.3 1861.15  5593.3 1902.48  5603.6 1905.97
#Mann= 8 ,-1 , 0
    4074    .035       0  4202.5     .07       0  4335.9    .035       0
  4596.9     .07       0  4769.3    .035       0  4910.4      .1       0
  4977.5     .05       0  4996.3      .1       0
Bank Sta=4977.5,4996.3
XS Rating Curve= 0 ,0
Exp/Cntr=0.3,0.1

Type RM Length L Ch R = 1 ,2161    ,495,495,495
BEGIN DESCRIPTION:
Bushwhack Creek 3.1
END DESCRIPTION:
XS GIS Cut Line= 4
      1895146.72     13901094.32      1895621.98     13900421.58
      1895663.21      13900332.6      1895786.91     13899720.62
#Sta/Elev= 30
  4124.6 1799.28  4190.3 1799.12  4274.9 1794.24  4376.6 1784.65  4402.6 1778.59
  4480.5 1775.02  4583.6 1762.92  4809.4 1758.23  4913.9 1756.59  4921.8 1754.22
  4928.6 1741.98  4939.6 1740.82  4949.8 1735.46  4967.6 1735.27  4968.1 1734.77
  4986.4 1735.27  5054.2 1737.83    5083 1743.69    5233  1746.7  5254.4 1749.81
  5272.8    1756  5324.8 1780.94    5386 1796.18  5438.1 1802.89  5520.6 1819.88
  5566.5 1819.32  5579.3 1822.31  5619.1 1820.89  5646.7 1829.32  5670.7 1833.54
#Mann= 7 ,-1 , 0
  4124.6     .07       0  4274.9    .035       0  4583.6     .07       0
  4809.4      .1       0  4967.6     .05       0  4986.4      .1       0
  5054.2      .1       0
Bank Sta=4967.6,4986.4
XS Rating Curve= 0 ,0
Exp/Cntr=0.3,0.1

Type RM Length L Ch R = 1 ,1666    ,303,303,303
BEGIN DESCRIPTION:
Bushwhack Creek 3.0
END DESCRIPTION:
XS GIS Cut Line= 4
      1895510.11     13901169.05      1895814.28     13900793.39
      1896051.96     13900499.84      1896325.01     13899974.98
#Sta/Elev= 30
  4054.5 1776.04  4122.9 1770.11  4208.8 1766.93    4228 1766.32  4568.4 1756.08
  4674.4 1754.15  4851.9 1751.27    4918 1750.89  4924.8 1747.38  4945.1 1745.91
  4967.6 1740.68  5013.5 1735.11    5014 1734.61  5032.3 1735.11  5049.9 1737.93
    5148 1740.62  5195.3 1757.79  5232.5 1776.77  5273.1 1807.37  5290.8 1818.05
  5310.3 1837.17  5323.8 1853.97  5327.2 1858.36  5330.6 1867.48  5336.3  1878.1
  5344.1 1885.22  5415.1 1920.38  5462.5 1940.65  5489.5  1950.4  5507.2 1953.01
#Mann= 9 ,-1 , 0
  4054.5    .035       0  4208.8     .07       0    4228    .035       0
  4568.4     .07       0  4674.4    .035       0  4851.9     .07       0
  4967.6      .1       0  5013.5     .05       0  5032.3      .1       0
Bank Sta=5013.5,5032.3
XS Rating Curve= 0 ,0
Exp/Cntr=0.3,0.1

Type RM Length L Ch R = 1 ,1363    ,422,422,422
BEGIN DESCRIPTION:
Bushwhack Creek 2.0
END DESCRIPTION:
XS GIS Cut Line= 4
      1895971.52     13901281.96        1896275.       13900675.
        1896375.       13900475.      1896574.99     13900125.02
#Sta/Elev= 30
  4097.8 1760.34  4255.6 1755.56  4579.9  1751.6  4783.5 1750.76  4844.6 1747.97
    4921  1744.7  4937.8 1740.78  4964.6 1738.54    4978 1731.94  4990.8 1729.91
  4991.3 1729.41  5009.7 1729.91  5013.3 1729.99  5063.7 1731.05  5074.1 1732.84
  5105.2 1744.21  5137.7 1760.86  5147.1 1766.91  5181.7 1789.65  5208.9 1811.96
  5226.1 1828.49  5229.6 1834.59  5233.1 1845.15  5236.1 1850.76    5240 1854.23
  5246.9 1869.35  5250.3 1872.33  5291.8 1896.68  5378.2 1940.47  5403.1 1950.82
#Mann= 9 ,-1 , 0
  4097.8    .035       0  4255.6     .07       0  4579.9    .035       0
  4844.6     .07       0  4990.8     .05       0  5009.7     .07       0
  5013.3      .1       0  5137.7     .07       0  5147.1      .1       0
Bank Sta=4990.8,5009.7
XS Rating Curve= 0 ,0
Exp/Cntr=0.3,0.1

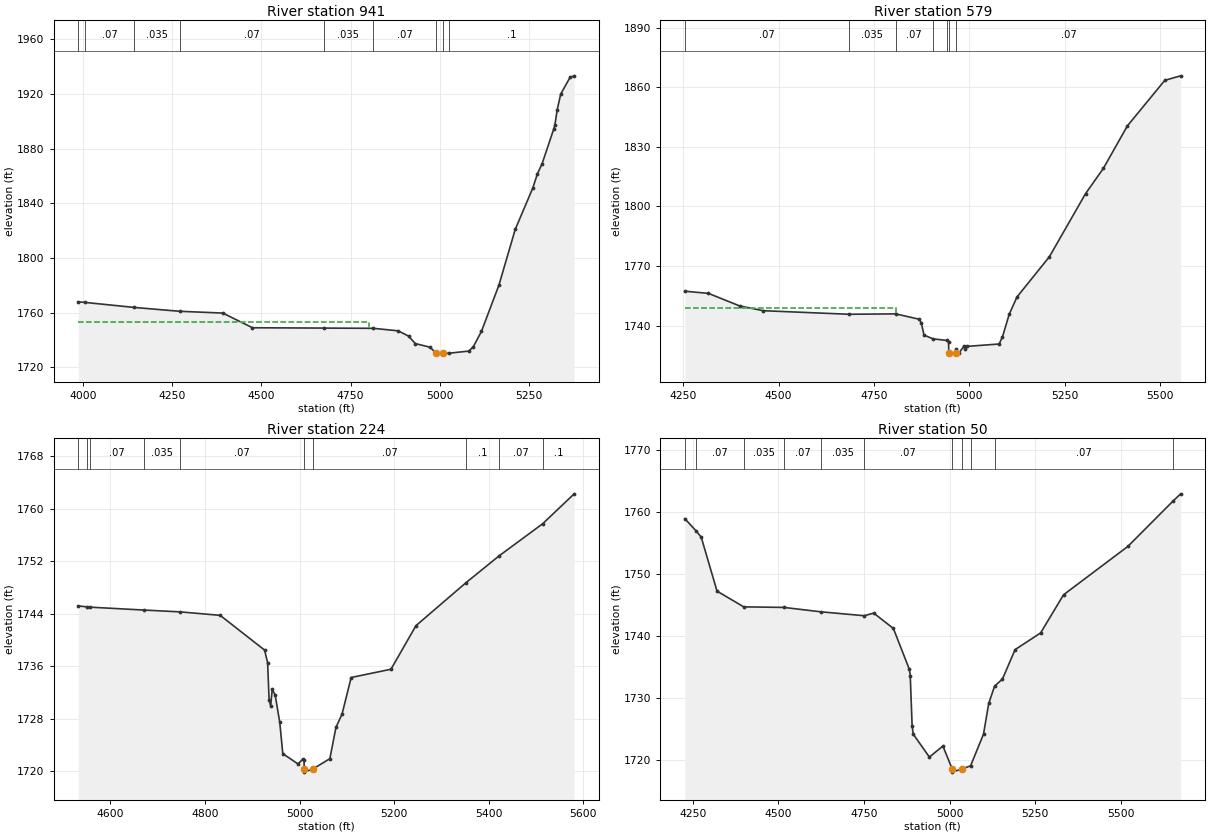
Type RM Length L Ch R = 1 ,941     ,362,362,362
BEGIN DESCRIPTION:
Bushwhack Creek 1.0
END DESCRIPTION:
XS GIS Cut Line= 4
      1896082.56     13901452.14      1896506.35     13900954.92
        1896725.       13900675.        1896875.       13900325.
#Sta/Elev= 30
  3987.2  1767.9  4005.8 1767.51  4143.4 1763.84  4271.1 1761.01    4392 1759.71
  4475.2 1748.97  4674.4 1748.74  4813.6 1748.57  4883.5 1746.72  4912.4 1742.89
  4931.4  1737.4  4973.2 1734.72  4989.9  1730.2  4990.4  1729.7  5008.8  1730.2
  5025.9 1730.38  5081.4 1731.93    5094 1735.13  5116.8 1746.37  5165.8 1780.23
  5211.5 1820.96  5260.5 1851.05  5273.5 1861.41  5286.6 1868.86  5319.2 1894.16
  5322.5 1897.12    5329 1908.26  5338.8 1919.77  5364.9 1931.97  5376.5 1933.12
#Mann= 9 ,-1 , 0
  3987.2    .035       0  4005.8     .07       0  4143.4    .035       0
  4271.1     .07       0  4674.4    .035       0  4813.6     .07       0
  4989.9     .05       0  5008.8     .07       0  5025.9      .1       0
#XS Ineff= 2 , 0
          4800.6 1753.39
Permanent Ineff=
       F       F
Bank Sta=4989.9,5008.8
XS Rating Curve= 0 ,0
Exp/Cntr=0.3,0.1

Type RM Length L Ch R = 1 ,579     ,355,355,355
BEGIN DESCRIPTION:
Bushwhack Creek 2.1
END DESCRIPTION:
XS GIS Cut Line= 5
      1896509.68     13901348.46      1896995.78     13900897.07
      1897037.45     13900820.68      1897096.48      13900706.1
      1897082.59       13900286.
#Sta/Elev= 30
  4254.4 1757.35  4316.4 1756.25  4398.1 1749.93  4459.7 1747.53    4684 1745.74
  4807.1 1745.93  4869.1 1743.22  4874.3 1741.38  4881.4 1735.25  4904.6 1733.37
  4940.7 1732.56  4945.6 1731.66  4946.6 1726.16  4947.1 1725.66  4965.5 1726.16
  4966.1 1728.22  4972.9 1726.25  4985.6 1729.52    4990 1728.05  4993.1 1729.55
  5078.3 1730.76    5087 1734.31  5104.9 1745.84  5125.2 1754.46  5210.1 1774.72
  5304.9  1806.5  5351.4 1819.16  5414.3 1840.55  5512.5 1863.53    5554  1865.8
#Mann= 7 ,-1 , 0
  4254.4     .07       0    4684    .035       0  4807.1     .07       0
  4904.6    .035       0  4940.7     .07       0  4946.6     .05       0
  4965.5     .07       0
#XS Ineff= 2 , 0
         4806.99 1748.74
Permanent Ineff=
       F       F
Bank Sta=4946.6,4965.5
XS Rating Curve= 0 ,0
Exp/Cntr=0.3,0.1

Type RM Length L Ch R = 1 ,224     ,174,174,174
BEGIN DESCRIPTION:
Bushwhack Creek 0.0
END DESCRIPTION:
XS GIS Cut Line= 4
      1896952.62     13901276.54      1897286.35     13901101.37
      1897381.21     13900852.18        1897326.     13900451.41
#Sta/Elev= 30
  4532.4 1745.23  4550.7 1745.08  4557.2 1745.04  4670.4  1744.6  4747.9 1744.32
  4832.3 1743.79  4926.1  1738.5  4932.5 1736.58  4935.7 1730.88    4939    1730
  4942.2 1732.51  4948.6 1731.62  4958.2 1727.47  4964.6 1722.72  4996.7 1721.15
  5007.7 1721.93  5009.6 1721.71  5009.8  1720.4  5010.3  1719.9  5028.7  1720.4
  5064.1 1721.95    5077 1726.73  5089.8 1728.73  5109.1 1734.32  5193.3 1735.58
  5246.1 1742.22  5351.2 1748.73  5421.9 1752.86  5513.9 1757.75  5580.5 1762.31
#Mann= 10 ,-1 , 0
  4532.4     .07       0  4550.7    .035       0  4557.2     .07       0
  4670.4    .035       0  4747.9     .07       0  5009.8     .05       0
  5028.7     .07       0  5351.2      .1       0  5421.9     .07       0
  5513.9      .1       0
Bank Sta=5009.8,5028.7
XS Rating Curve= 0 ,0
Exp/Cntr=0.3,0.1

Type RM Length L Ch R = 1 ,50      ,0,0,0
BEGIN DESCRIPTION:
Bushwhack Creek 0.1
END DESCRIPTION:
XS GIS Cut Line= 4
      1896823.01     13901479.56      1897453.25     13901101.93
      1897507.94     13901026.41      1897372.52     13900422.26
#Sta/Elev= 30
    4227 1758.95  4260.8 1756.91  4274.9 1755.96  4321.1 1747.25    4399 1744.71
  4516.1 1744.62  4624.2 1743.91  4750.5 1743.28  4778.5  1743.7  4835.8 1741.22
  4882.5 1734.61    4885 1733.62  4890.5 1725.48  4893.7 1724.17  4940.8 1720.47
  4980.3 1722.25  5007.5 1718.54    5008 1718.04  5034.8 1718.54    5061 1719.05
  5098.8 1724.17  5114.1 1729.14  5131.2 1731.92  5154.1 1733.06    5191 1737.81
  5265.6 1740.51  5332.4 1746.66    5520 1754.46  5650.8 1761.72  5674.1 1762.95
#Mann= 11 ,-1 , 0
    4227      .1       0  4260.8     .07       0    4399    .035       0
  4516.1     .07       0  4624.2    .035       0  4750.5     .07       0
  5007.5     .05       0  5034.8     .07       0    5061      .1       0
  5131.2     .07       0  5650.8      .1       0
Bank Sta=5007.5,5034.8
XS Rating Curve= 0 ,0
Exp/Cntr=0.3,0.1

Chan Stop Cuts=-1
Use User Specified Reach Order=0
Composite Channel Slope=5