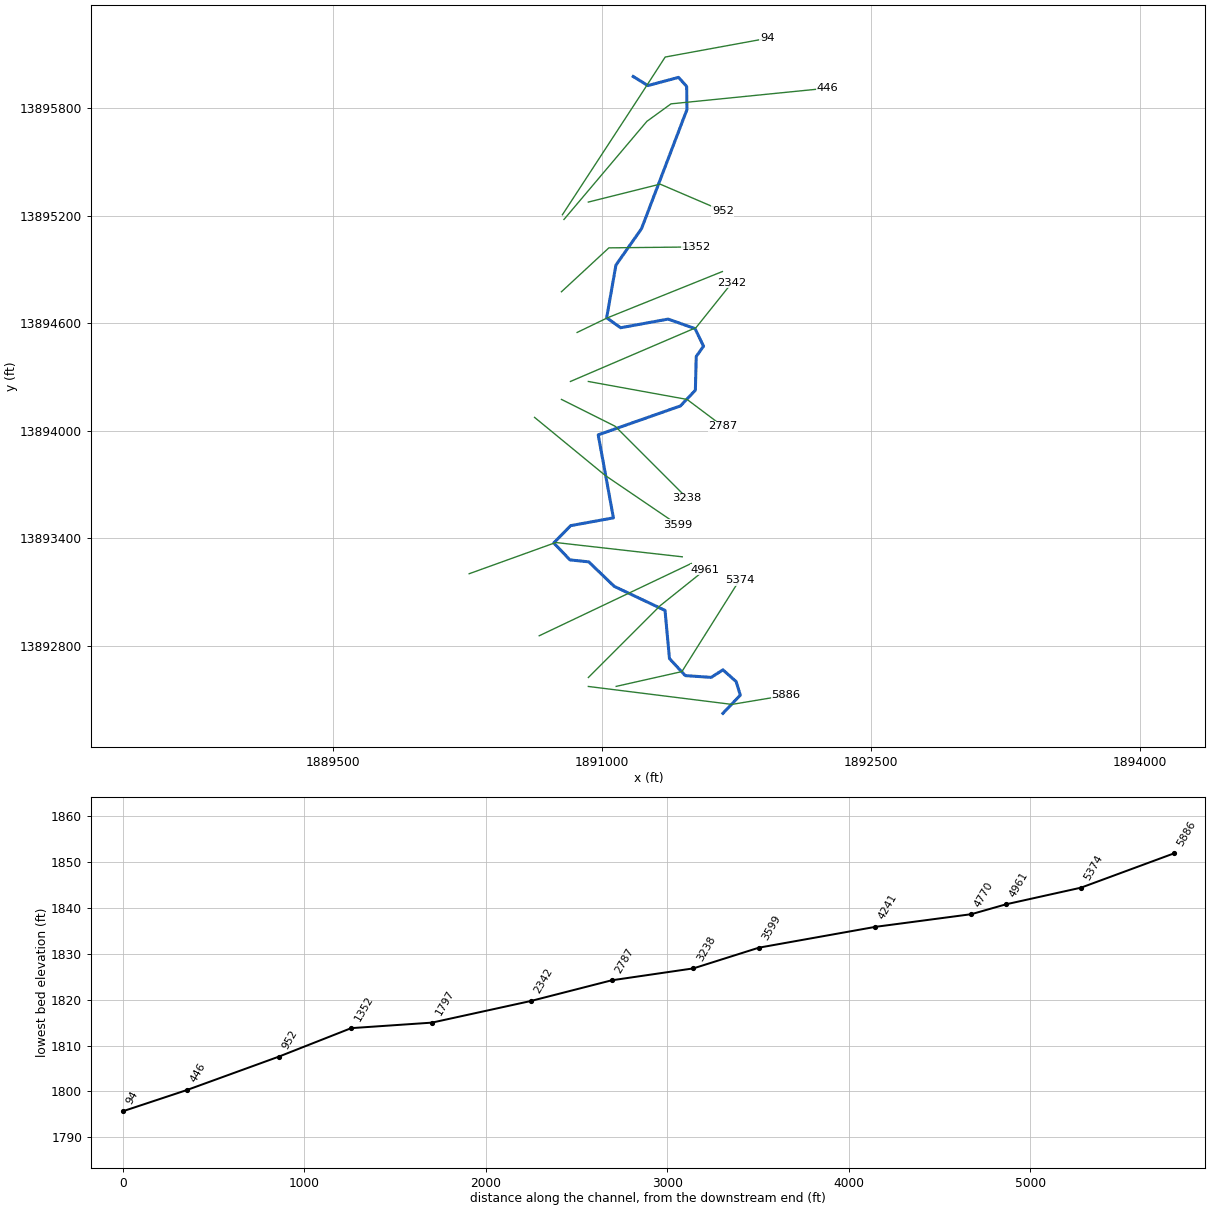
--- Calf Run.prj (project) ---

Proj Title=Calf Run Base Level Engineering
Current Plan=p01
Default Exp/Contr=0.3,0.1
English Units
Geom File=g01
Flow File=f01
Plan File=p01
Y Axis Title=Elevation
X Axis Title(PF)=Main Channel Distance
X Axis Title(XS)=Station
BEGIN DESCRIPTION:
Calf Run
END DESCRIPTION:
DSS Export Rating Curves= 0
DSS Export Rating Curve Sorted= 0
DSS Export Volume Flow Curves= 0
DXF OffsetX= 0
DXF OffsetY= 0
DXF ScaleX= 1
DXF ScaleY= 10

--- Calf Run.p01 (plan) ---

Plan Title=Multiple Run
Short Identifier=Multiple
Geom File=g01
Flow File=f01
Subcritical Flow
K Sum by GR= 0
Std Step Tol= 0.01
Critical Tol= 0.01
Num of Std Step Trials= 20
Max Error Tol= 0.3
Flow Tol Ratio= 0.001
Split Flow NTrial= 30
Split Flow Tol= 0.02
Split Flow Ratio= 0.02
Log Output Level= 0
Friction Slope Method= 1
Unsteady Friction Slope Method= 2
Unsteady Bridges Friction Slope Method= 1
Parabolic Critical Depth
Global Vel Dist=  1 , 1 , 1
Global Log Level= 0
CheckData=True
Encroach Param= -1, 0, 0, 0
BEGIN DESCRIPTION:
Multiple Run
END DESCRIPTION:

--- Calf Run.f01 (steady flow) ---

Flow Title=Multiple
Program Version=4.10
Number of Profiles= 7
Profile Names=10-year,25-year,50-year,1pct_min,100-year,1pct_plu,500-year
River Rch & RM=Calf Run,Reach-1         ,5886
    1705    2958    4170    2838    5662   11298   10316
Boundary for River Rch & Prof#=Calf Run,Reach-1         , 1
Up Type= 0
Dn Type= 3
Dn Slope=0.01
Boundary for River Rch & Prof#=Calf Run,Reach-1         , 2
Up Type= 0
Dn Type= 3
Dn Slope=0.01
Boundary for River Rch & Prof#=Calf Run,Reach-1         , 3
Up Type= 0
Dn Type= 3
Dn Slope=0.01
Boundary for River Rch & Prof#=Calf Run,Reach-1         , 4
Up Type= 0
Dn Type= 3
Dn Slope=0.01
Boundary for River Rch & Prof#=Calf Run,Reach-1         , 5
Up Type= 0
Dn Type= 3
Dn Slope=0.01
Boundary for River Rch & Prof#=Calf Run,Reach-1         , 6
Up Type= 0
Dn Type= 3
Dn Slope=0.01
Boundary for River Rch & Prof#=Calf Run,Reach-1         , 7
Up Type= 0
Dn Type= 3
Dn Slope=0.01
DSS Import GetInterval= 0
DSS Import GetPeak= 0
DSS Import FillOption= 0

--- Calf Run.g01 (geometry) ---

Geom Title=Existing Conditions
Program Version=4.10

River Reach=Calf Run        ,Reach-1
Reach XY= 30
        1891675.       13892425.      1891771.98     13892526.64
      1891748.96     13892601.95      1891675.11     13892667.69
      1891609.84     13892625.65      1891465.18     13892635.46
      1891377.16     13892730.43       1891352.3     13892998.91
      1891068.94     13893133.14      1890927.43     13893269.48
      1890822.54     13893280.52      1890732.06       13893375.
      1890826.44     13893471.46      1891064.72     13893514.84
      1890979.97     13893977.59      1891438.24     13894138.61
      1891521.47     13894226.45      1891526.38     13894414.56
      1891566.96     13894471.74      1891519.59     13894569.74
      1891369.43     13894622.72      1891104.76      13894574.5
      1891027.07     13894630.24      1891078.62      13894923.5
      1891221.17     13895126.58      1891474.49     13895790.22
      1891472.92     13895919.79      1891427.59     13895970.03
      1891256.78     13895924.32        1891175.       13895975.

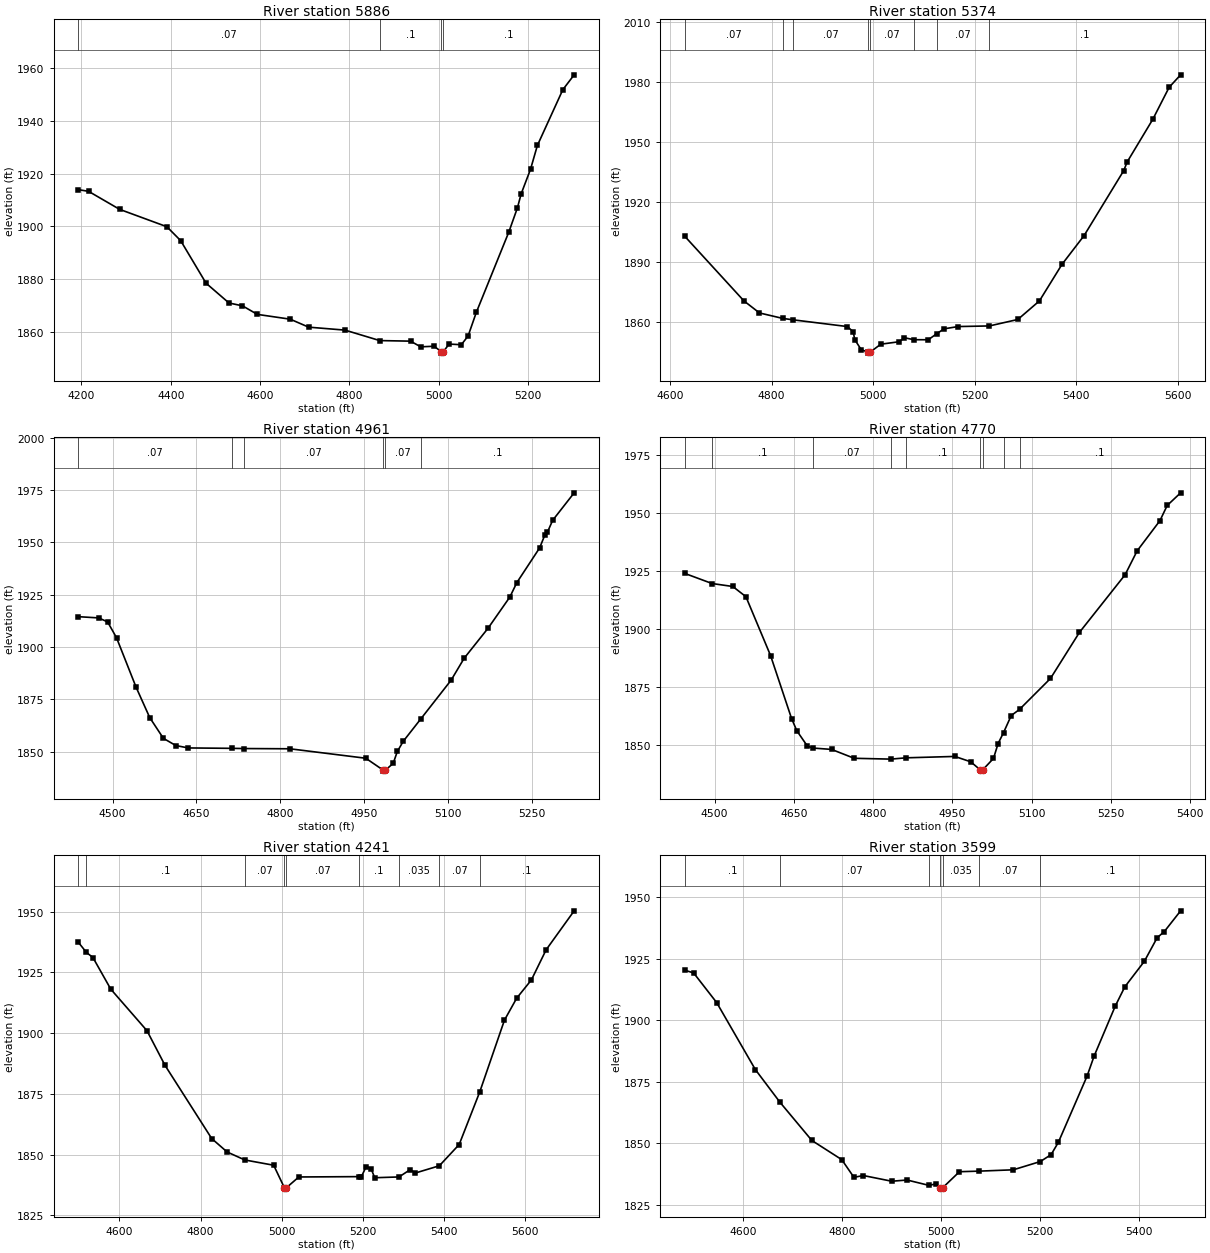
Type RM Length L Ch R = 1 ,5886    ,512,512,512
BEGIN DESCRIPTION:
Calf Run 11.0
END DESCRIPTION:
XS GIS Cut Line= 3
      1890924.98       13892575.        1891725.       13892475.
      1892025.01       13892525.
#Sta/Elev= 30
  4193.1 1913.94    4216  1913.3  4285.6 1906.45  4391.4 1899.85  4422.3 1894.56
  4479.1  1878.4  4530.5 1870.87  4560.7 1869.79    4594 1866.54  4667.6 1864.72
  4708.9 1861.69  4790.5 1860.56  4868.1 1856.59  4937.1 1856.37  4959.8 1854.22
    4990 1854.43  5006.2 1852.32  5006.4 1851.82  5010.3 1852.32  5023.4 1855.27
  5050.8 1855.01    5066 1858.35  5084.3 1867.27  5157.2 1897.84  5176.6 1907.11
  5184.6 1912.25  5205.9 1921.75  5221.1 1930.72  5278.2 1951.95  5303.5 1957.57
#Mann= 4 ,-1 , 0
  4193.1     .07       0  4868.1      .1       0  5006.2     .05       0
  5010.3      .1       0
Bank Sta=5006.2,5010.3
XS Rating Curve= 0 ,0
Exp/Cntr=0.3,0.1

Type RM Length L Ch R = 1 ,5374    ,413,413,413
BEGIN DESCRIPTION:
Calf Run 10.0
END DESCRIPTION:
XS GIS Cut Line= 3
      1891080.21     13892575.47      1891446.52     13892657.93
      1891766.44     13893166.62
#Sta/Elev= 30
  4628.9 1902.78  4745.4 1870.47    4776 1864.45  4821.8 1861.72  4842.3 1861.01
  4948.7 1857.66  4960.5 1855.09  4963.6 1851.12  4976.3 1846.08  4989.8 1844.86
  4990.1 1844.36  4993.9 1844.86  5014.9 1848.83  5050.8 1850.05  5061.4 1852.05
  5080.3 1851.07  5108.4 1851.05    5125 1854.07  5139.4 1856.51  5167.2 1857.65
  5228.8 1857.96  5284.7 1861.19  5327.2 1870.47  5371.7 1888.76  5415.2 1903.15
  5493.2 1935.62  5500.1 1940.01  5550.5  1961.3  5582.7 1977.32  5605.3 1983.55
#Mann= 8 ,-1 , 0
  4628.9     .07       0  4821.8    .035       0  4842.3     .07       0
  4989.8     .05       0  4993.9     .07       0  5080.3      .1       0
    5125     .07       0  5228.8      .1       0
Bank Sta=4989.8,4993.9
XS Rating Curve= 0 ,0
Exp/Cntr=0.3,0.1

Type RM Length L Ch R = 1 ,4961    ,191,191,191
BEGIN DESCRIPTION:
Calf Run 9.0
END DESCRIPTION:
XS GIS Cut Line= 3
        1890925.       13892625.        1891325.       13893025.
      1891574.96     13893224.97
#Sta/Elev= 30
  4438.9 1914.48  4475.3 1913.89  4491.2 1911.98  4507.1 1904.45  4542.1  1880.8
  4566.5 1866.28  4590.9 1856.39  4613.1 1852.95  4635.4 1851.81  4713.3 1851.62
  4734.8 1851.52  4816.8 1851.41  4952.5 1846.89  4983.4 1841.24  4983.7 1840.74
  4987.6 1841.24  5001.4 1844.43  5008.8 1850.13  5019.5 1855.03  5050.5 1865.59
  5104.9 1884.17  5128.2 1894.64  5170.8 1908.94  5209.8 1923.85  5222.3 1930.75
    5263 1947.31  5272.2 1953.37    5277 1954.86  5286.3 1960.48  5324.7 1973.61
#Mann= 6 ,-1 , 0
  4438.9     .07       0  4713.3    .035       0  4734.8     .07       0
  4983.4     .05       0  4987.6     .07       0  5050.5      .1       0
Bank Sta=4983.4,4987.6
XS Rating Curve= 0 ,0
Exp/Cntr=0.3,0.1

Type RM Length L Ch R = 1 ,4770    ,529,529,529
BEGIN DESCRIPTION:
Mapping XS 2630976a
END DESCRIPTION:
XS GIS Cut Line= 2
      1890651.19     13892857.56      1891498.66     13893260.54
#Sta/Elev= 30
  4443.6  1923.9  4495.2 1919.54  4534.5 1918.26  4559.3 1913.85  4605.9 1888.48
  4645.7 1861.27  4655.7 1855.98  4675.6  1849.4  4685.9 1848.55  4721.4 1847.96
  4764.2 1844.13  4833.7 1843.77  4862.1 1844.33  4954.7 1844.93  4984.8 1842.61
    5003 1839.09  5003.3 1838.59  5007.2 1839.09  5027.8 1844.06  5036.6 1850.51
  5046.9 1855.23  5061.4 1862.57  5077.1 1865.23  5135.7 1878.58  5190.5 1898.46
  5276.9 1923.32  5299.7 1933.64  5342.8 1946.65  5356.6 1953.23    5382 1958.68
#Mann= 9 ,-1 , 0
  4443.6     .07       0  4495.2      .1       0  4685.9     .07       0
  4833.7    .035       0  4862.1      .1       0    5003     .05       0
  5007.2      .1       0  5046.9     .07       0  5077.1      .1       0
Bank Sta=5003,5007.2
XS Rating Curve= 0 ,0
Exp/Cntr=0.3,0.1

Type RM Length L Ch R = 1 ,4241    ,642,642,642
BEGIN DESCRIPTION:
Calf Run 8.0
END DESCRIPTION:
XS GIS Cut Line= 3
      1890260.53     13893203.32      1890743.37     13893377.38
      1891448.52     13893297.68
#Sta/Elev= 30
  4498.5 1937.39  4518.6 1933.19  4534.5 1931.12  4578.5 1918.11  4667.8 1901.01
  4712.4 1886.72  4827.5 1856.63  4865.5 1851.11  4909.1 1847.83  4980.3 1845.66
  5006.9 1836.33  5007.1 1835.83  5011.1 1836.33  5042.3 1840.83  5189.8 1840.97
  5196.3 1840.84  5208.4 1845.08  5220.5 1844.25  5229.5 1840.52  5289.4 1840.84
  5317.1 1843.86  5329.1 1842.43  5388.9 1845.44  5437.8 1854.18  5488.5  1875.8
  5549.5 1905.36  5579.7  1914.4    5616 1921.92  5652.2 1934.28  5721.4 1950.33
#Mann= 9 ,-1 , 0
  4498.5     .07       0  4518.6      .1       0  4909.1     .07       0
  5006.9     .05       0  5011.1     .07       0  5189.8      .1       0
  5289.4    .035       0  5388.9     .07       0  5488.5      .1       0
Bank Sta=5006.9,5011.1
XS Rating Curve= 0 ,0
Exp/Cntr=0.3,0.1

Type RM Length L Ch R = 1 ,3599    ,361,361,361
BEGIN DESCRIPTION:
Calf Run 7.0
END DESCRIPTION:
XS GIS Cut Line= 3
        1890625.       13894075.      1891019.77     13893750.64
      1891424.98     13893475.02
#Sta/Elev= 30
    4483 1920.28  4500.8 1919.19  4547.4 1907.12  4625.5 1879.88  4675.4 1866.55
  4739.5 1851.08  4799.8  1843.3  4824.5 1836.09  4843.4 1836.83  4900.7 1834.51
  4931.8    1835  4975.9 1832.83    4990 1833.42    4999  1831.8  4999.3  1831.3
  5003.3  1831.8  5037.5 1838.38  5077.9 1838.62  5146.3 1839.16  5200.8 1842.52
  5222.5 1845.32    5237 1850.26  5295.1 1877.23  5309.4 1885.41  5352.1 1905.73
  5371.3 1913.52  5410.8 1923.91  5436.6 1933.49  5451.1 1936.01    5484 1944.43
#Mann= 7 ,-1 , 0
    4483      .1       0  4675.4     .07       0  4975.9    .035       0
    4999    .035       0  5003.3    .035       0  5077.9     .07       0
  5200.8      .1       0
Bank Sta=4999,5003.3
XS Rating Curve= 0 ,0
Exp/Cntr=0.3,0.1

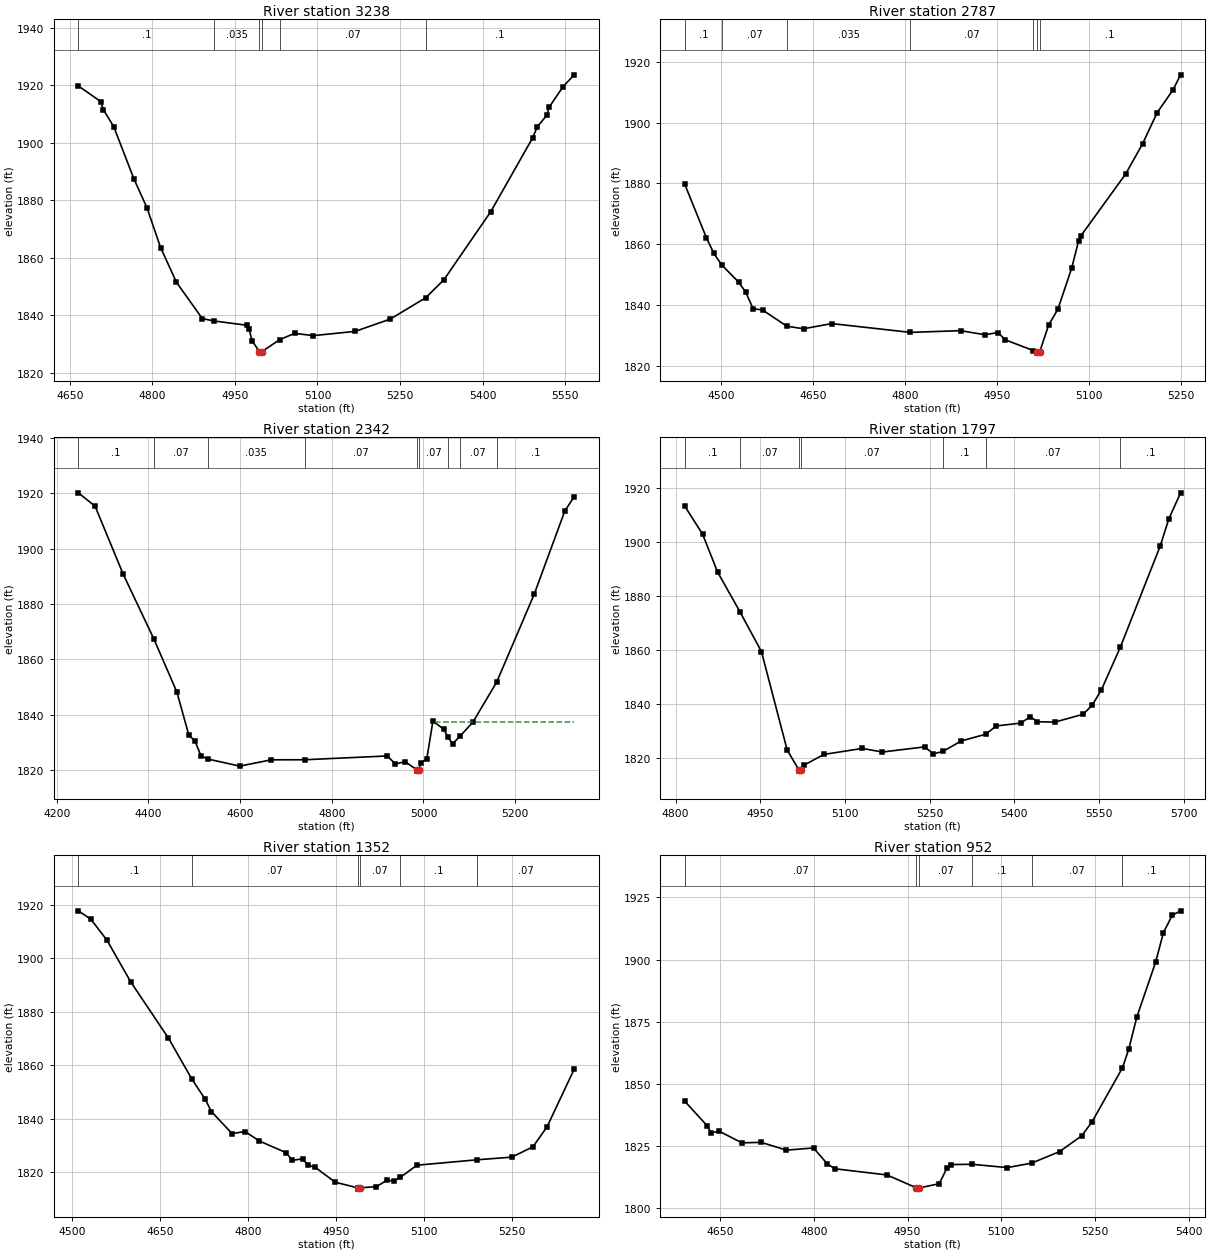
Type RM Length L Ch R = 1 ,3238    ,451,451,451
BEGIN DESCRIPTION:
Calf Run 6.0
END DESCRIPTION:
XS GIS Cut Line= 3
      1890775.03     13894174.99        1891075.       13894025.
      1891475.02     13893624.98
#Sta/Elev= 30
  4665.4  1919.7    4706 1914.28  4710.9 1911.45  4729.8 1905.51  4766.4 1887.38
  4790.2 1877.29  4814.9  1863.5  4843.8  1851.4  4890.8 1838.79  4912.6 1837.96
  4971.3 1836.49  4975.9 1835.07  4981.1 1831.09  4994.6 1827.29  4994.9 1826.79
  4998.9 1827.29  5031.4 1831.47  5058.4 1833.67  5092.4 1832.87  5168.7 1834.36
  5232.4 1838.64  5296.7 1846.05  5329.9 1852.32  5414.8 1875.94  5491.2 1901.69
  5499.6 1905.53  5516.6 1909.46  5520.9 1912.26  5546.3 1919.45  5566.5 1923.56
#Mann= 6 ,-1 , 0
  4665.4      .1       0  4912.6    .035       0  4994.6    .035       0
  4998.9    .035       0  5031.4     .07       0  5296.7      .1       0
Bank Sta=4994.6,4998.9
XS Rating Curve= 0 ,0
Exp/Cntr=0.3,0.1

Type RM Length L Ch R = 1 ,2787    ,445,445,445
BEGIN DESCRIPTION:
Calf Run 5.0
END DESCRIPTION:
XS GIS Cut Line= 3
      1890925.03     13894274.99        1891475.       13894175.
      1891675.01     13894024.99
#Sta/Elev= 30
  4440.5 1879.68  4475.8  1862.1    4488 1856.96  4500.9 1853.16  4528.6 1847.49
  4539.8 1844.26    4552 1838.79  4567.3 1838.39  4607.1 1833.03  4634.3  1832.2
  4680.1 1833.91  4808.6 1831.01  4890.5 1831.58  4930.1 1830.24  4951.5 1830.96
  4963.7 1828.53  5009.1 1825.05  5015.4 1824.69  5015.6 1824.19  5019.7 1824.69
  5034.2 1833.46  5049.2 1838.61  5071.7 1852.12  5082.9 1861.01  5086.7 1862.74
  5159.9 1883.13  5187.5 1893.07  5211.3 1903.31  5236.7 1910.64  5249.5 1915.71
#Mann= 7 ,-1 , 0
  4440.5      .1       0  4500.9     .07       0  4607.1    .035       0
  4808.6     .07       0  5009.1      .1       0  5015.4     .05       0
  5019.7      .1       0
Bank Sta=5015.4,5019.7
XS Rating Curve= 0 ,0
Exp/Cntr=0.3,0.1

Type RM Length L Ch R = 1 ,2342    ,545,545,545
BEGIN DESCRIPTION:
Calf Run 4.0
END DESCRIPTION:
XS GIS Cut Line= 3
      1890825.02     13894275.01        1891525.       13894575.
      1891724.99     13894824.99
#Sta/Elev= 30
  4247.1 1920.18  4283.6 1915.37  4344.7 1890.91    4412 1867.37  4462.2  1848.2
  4488.3  1832.6  4501.4 1830.68  4514.4  1825.3  4529.3 1824.07  4599.3  1821.5
  4667.8 1823.77  4740.8  1823.8    4921 1825.17  4938.8 1822.28  4959.9  1823.1
  4985.4 1820.19  4985.8 1819.69    4990 1820.19  4994.2 1822.68  5007.3  1824.1
  5020.7 1837.77  5044.2 1834.81  5053.7 1831.96  5063.4 1829.54  5079.6 1832.24
  5108.2 1837.45  5159.7 1851.82    5242 1883.71  5308.6 1913.72  5328.8 1918.72
#Mann= 9 ,-1 , 0
  4247.1      .1       0    4412     .07       0  4529.3    .035       0
  4740.8     .07       0  4985.4     .05       0    4990     .07       0
  5053.7      .1       0  5079.6     .07       0  5159.7      .1       0
#XS Ineff= 2 , 0
                         5024.78         1837.45
Permanent Ineff=
       F       F
Bank Sta=4985.4,4990
XS Rating Curve= 0 ,0
Exp/Cntr=0.3,0.1

Type RM Length L Ch R = 1 ,1797    ,445,445,445
BEGIN DESCRIPTION:
Calf Run 3.0
END DESCRIPTION:
XS GIS Cut Line= 3
      1890862.37     13894548.24      1891030.98     13894629.69
      1891672.03     13894887.75
#Sta/Elev= 30
  4816.3  1913.1  4847.8 1902.76  4874.5 1888.67  4913.9 1874.04  4952.1 1859.24
  4997.7 1822.75  5018.3 1815.48  5018.6 1814.98  5022.9 1815.48    5027 1817.13
  5062.6 1821.16  5130.8 1823.39  5166.1 1822.05  5241.3 1823.96  5256.6 1821.38
  5273.4 1822.27  5305.8 1826.13  5349.3 1828.65  5368.1 1831.72  5411.9 1832.78
    5428 1835.16    5441 1833.27  5471.8 1833.14  5521.8 1836.03    5538 1839.38
  5554.2 1845.06  5587.7 1860.82  5658.6 1898.44  5673.8 1908.49  5694.6 1918.06
#Mann= 7 ,-1 , 0
  4816.3      .1       0  4913.9     .07       0  5018.3     .05       0
  5022.9     .07       0  5273.4      .1       0  5349.3     .07       0
  5587.7      .1       0
Bank Sta=5018.3,5022.9
XS Rating Curve= 0 ,0
Exp/Cntr=0.3,0.1

Type RM Length L Ch R = 1 ,1352    ,400,400,400
BEGIN DESCRIPTION:
Calf Run 2.0
END DESCRIPTION:
XS GIS Cut Line= 3
      1890774.97     13894774.97      1891039.44     13895019.82
        1891525.       13895025.
#Sta/Elev= 30
  4510.8 1917.82    4532 1914.71  4559.6 1906.86    4600 1891.32  4664.5 1870.24
  4704.6 1854.89  4727.3 1847.37  4737.9 1842.76  4773.1 1834.55  4795.3 1835.31
  4819.8 1831.76  4865.9 1827.36  4875.5  1824.5  4893.5 1825.13  4902.5 1822.69
  4914.5 1822.01    4949 1816.37  4987.2 1814.28  4987.5 1813.78  4991.8 1814.28
  5019.5 1814.72  5037.5 1817.13  5049.1 1816.79    5060 1818.15  5088.5 1822.72
  5191.4 1824.75  5250.5 1825.74  5286.5 1829.61  5310.5 1837.05  5356.8 1858.61
#Mann= 6 ,-1 , 0
  4510.8      .1       0  4704.6     .07       0  4987.2     .05       0
  4991.8     .07       0    5060      .1       0  5191.4     .07       0
Bank Sta=4987.2,4991.8
XS Rating Curve= 0 ,0
Exp/Cntr=0.3,0.1

Type RM Length L Ch R = 1 ,952     ,506,506,506
BEGIN DESCRIPTION:
Calf Run 1.0
END DESCRIPTION:
XS GIS Cut Line= 3
      1890925.03     13895275.01        1891325.       13895375.
      1891675.03     13895224.99
#Sta/Elev= 30
  4593.6 1842.94  4629.4 1833.07  4635.6 1830.25  4648.8 1830.85  4685.1 1826.19
  4715.6  1826.4  4756.2 1823.26  4799.5 1824.14  4821.1 1817.86  4833.5 1815.76
    4917 1813.27  4964.2 1808.06  4964.5 1807.56  4968.8 1808.06  5000.5 1809.74
  5013.2 1816.15  5019.8 1817.46  5053.3 1817.56  5109.5 1816.23  5148.5 1818.04
  5193.3  1822.7  5228.6 1829.06    5245 1834.67  5293.7 1856.42  5303.7 1863.89
  5316.8 1876.99  5346.6 1898.88  5359.2 1910.85  5373.4 1917.87  5386.7 1919.63
#Mann= 6 ,-1 , 0
  4593.6     .07       0  4964.2     .05       0  4968.8     .07       0
  5053.3      .1       0  5148.5     .07       0  5293.7      .1       0
Bank Sta=4964.2,4968.8
XS Rating Curve= 0 ,0
Exp/Cntr=0.3,0.1

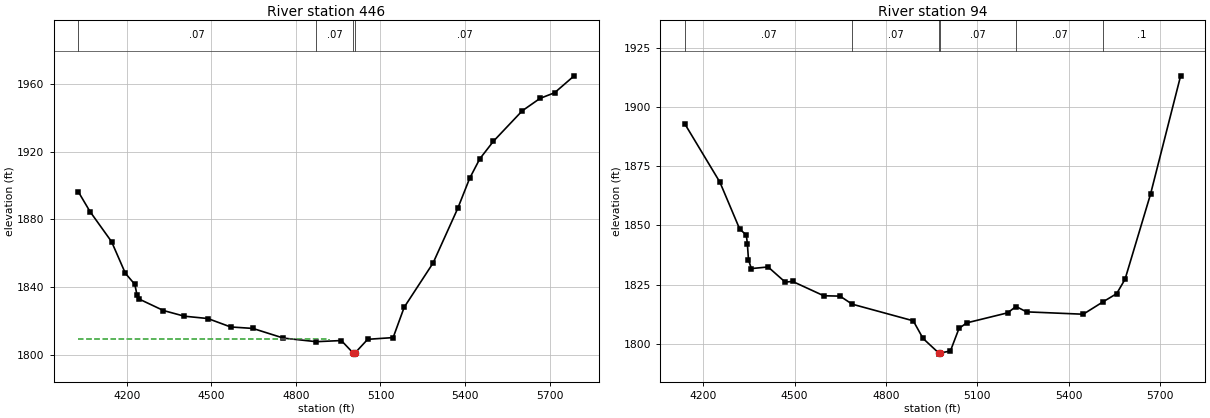
Type RM Length L Ch R = 1 ,446     ,352,352,352
BEGIN DESCRIPTION:
Calf Run 0.0
END DESCRIPTION:
XS GIS Cut Line= 4
      1890789.02     13895178.02      1891250.92     13895724.71
      1891385.67     13895822.48      1892259.01     13895910.05
#Sta/Elev= 30
  4027.6 1896.31    4069 1884.63  4145.6  1866.8  4194.5 1848.12  4228.1 1841.55
    4236 1835.19  4244.7 1832.77  4329.8 1826.08  4403.7 1822.74  4487.3 1821.35
  4568.2 1816.37    4647  1815.5  4755.7 1809.78  4871.9 1807.66  4961.1 1808.33
    5004  1800.8  5004.3  1800.3  5008.7  1800.8  5054.6 1809.06    5145 1810.08
  5184.2 1828.01  5286.7 1854.17  5374.2 1886.46  5416.4 1904.22  5452.6 1915.82
  5500.8 1926.17  5603.3 1944.22  5666.6 1951.58  5717.9 1954.87  5787.5  1964.9
#Mann= 4 ,-1 , 0
  4027.6     .07       0  4871.9     .07       0    5004     .05       0
  5008.7     .07       0
#XS Ineff= 2 , 0
         4918.81 1809.15
Permanent Ineff=
       F       F
Bank Sta=5004,5008.7
XS Rating Curve= 0 ,0
Exp/Cntr=0.3,0.1

Type RM Length L Ch R = 1 ,94      ,0,0,0
BEGIN DESCRIPTION:
Calf Run 0.1
END DESCRIPTION:
XS GIS Cut Line= 4
      1890780.31     13895204.13      1891211.32     13895864.25
      1891353.25     13896083.41       1891922.3     13896187.68
#Sta/Elev= 30
  4139.8 1892.87    4255 1868.27  4320.1 1848.45  4341.7 1845.98  4345.3  1842.2
  4348.9 1835.52  4358.3 1831.79  4413.3 1832.48  4469.6 1826.07  4493.5 1826.38
  4596.1 1820.32  4649.5 1820.17  4689.2 1816.78  4889.9 1809.75  4922.1  1802.3
  4973.4 1796.19  4973.7 1795.69  4978.2 1796.19  5011.8 1796.98  5040.1 1806.52
  5065.1 1808.87  5199.8 1813.12  5227.3 1815.79    5262 1813.53    5448 1812.53
  5514.3 1817.86  5557.8 1821.21  5585.3 1827.29    5669  1863.2  5767.8 1913.14
#Mann= 6 ,-1 , 0
  4139.8     .07       0  4689.2     .07       0  4973.4     .05       0
  4978.2     .07       0  5227.3     .07       0  5514.3      .1       0
Bank Sta=4973.4,4978.2
XS Rating Curve= 0 ,0
Exp/Cntr=0.3,0.1

Chan Stop Cuts=-1
Use User Specified Reach Order=0
Composite Channel Slope=5