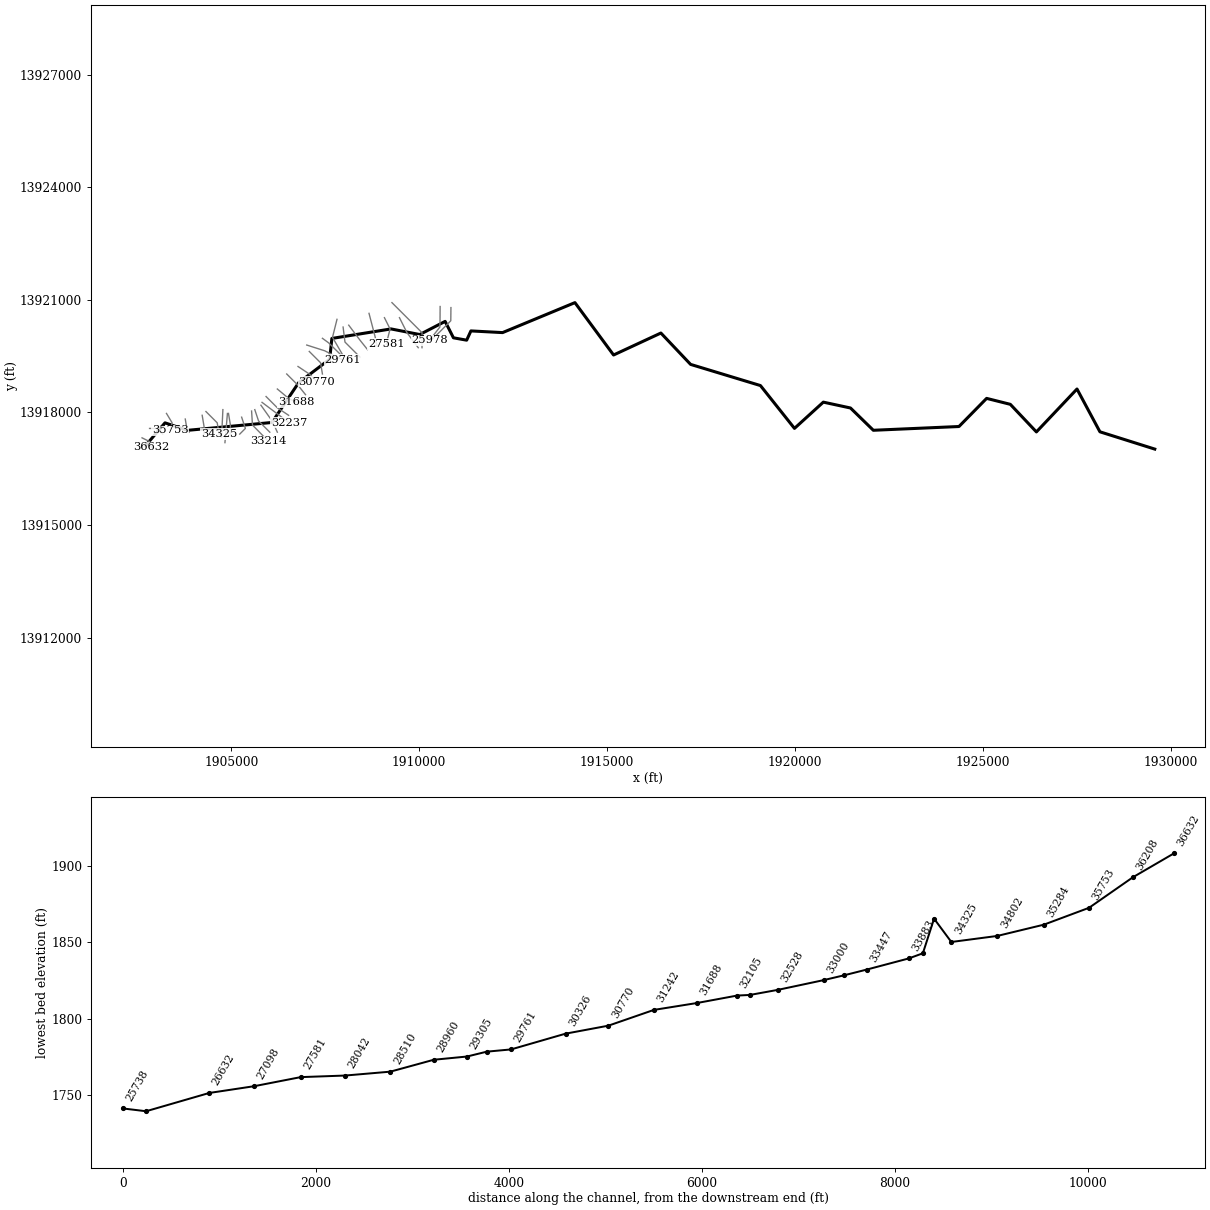
--- Camp Meeting Creek.prj (project) ---

Proj Title=Camp Meeting Creek Base Level Engineering
Current Plan=p01
Default Exp/Contr=0.3,0.1
English Units
Geom File=g01
Flow File=f01
Plan File=p01
Y Axis Title=Elevation
X Axis Title(PF)=Main Channel Distance
X Axis Title(XS)=Station
BEGIN DESCRIPTION:
Camp Meeting Creek
END DESCRIPTION:
DSS Export Rating Curves= 0
DSS Export Rating Curve Sorted= 0
DSS Export Volume Flow Curves= 0
DXF OffsetX= 0
DXF OffsetY= 0
DXF ScaleX= 1
DXF ScaleY= 10

--- Camp Meeting Creek.p01 (plan) ---

Plan Title=Multiple Run
Short Identifier=Multiple
Geom File=g01
Flow File=f01
Subcritical Flow
K Sum by GR= 0
Std Step Tol= 0.01
Critical Tol= 0.01
Num of Std Step Trials= 20
Max Error Tol= 0.3
Flow Tol Ratio= 0.001
Split Flow NTrial= 30
Split Flow Tol= 0.02
Split Flow Ratio= 0.02
Log Output Level= 0
Friction Slope Method= 1
Unsteady Friction Slope Method= 2
Unsteady Bridges Friction Slope Method= 1
Parabolic Critical Depth
Global Vel Dist=  1 , 1 , 1
Global Log Level= 0
CheckData=True
Encroach Param= -1, 0, 0, 0
BEGIN DESCRIPTION:
Multiple Run
END DESCRIPTION:

--- Camp Meeting Creek.f01 (steady flow) ---

Flow Title=Multiple
Program Version=4.10
Number of Profiles= 7
Profile Names=10-year,25-year,50-year,1pct_min,100-year,1pct_plu,500-year
River Rch & RM=Camp Meeting Cre,Reach-1         ,36632
     581     955    1299     858    1712    3416    2928
River Rch & RM=Camp Meeting Cre,Reach-1         ,34802
    1394    2409    3389    2304    4597    9172    8352
River Rch & RM=Camp Meeting Cre,Reach-1         ,29305
    2075    3660    5218    3588    7160   14286   13325
River Rch & RM=Camp Meeting Cre,Reach-1         ,25978
    2346    4161    5955    4109    8198   16357   15359
River Rch & RM=Camp Meeting Cre,Reach-1         ,24896
    2528    4500    6453    4461    8901   17760   16741
River Rch & RM=Camp Meeting Cre,Reach-1         ,23960
    2894    5178    7451    5165   10306   20562   19495
River Rch & RM=Camp Meeting Cre,Reach-1         ,21175
    3233    5808    8381    5824   11620   23184   22085
River Rch & RM=Camp Meeting Cre,Reach-1         ,19318
    3533    6375    9224    6425   12821   25580   24491
River Rch & RM=Camp Meeting Cre,Reach-1         ,18872
    3961    7166   10388    7245   14456   28844   27687
River Rch & RM=Camp Meeting Cre,Reach-1         ,14498
    4134    7488   10863    7581   15126   30181   29005
River Rch & RM=Camp Meeting Cre,Reach-1         ,12232
    6050   11125   16304   11482   22909   45709   44735
River Rch & RM=Camp Meeting Cre,Reach-1         ,8723
    6340   11657   17081   12023   23990   47866   46802
River Rch & RM=Camp Meeting Cre,Reach-1         ,2982
    6373   11702   17130   12045   24033   47952   46787
Boundary for River Rch & Prof#=Camp Meeting Cre,Reach-1         , 1
Up Type= 0
Dn Type= 3
Dn Slope=0.007
Boundary for River Rch & Prof#=Camp Meeting Cre,Reach-1         , 2
Up Type= 0
Dn Type= 3
Dn Slope=0.007
Boundary for River Rch & Prof#=Camp Meeting Cre,Reach-1         , 3
Up Type= 0
Dn Type= 3
Dn Slope=0.007
Boundary for River Rch & Prof#=Camp Meeting Cre,Reach-1         , 4
Up Type= 0
Dn Type= 3
Dn Slope=0.007
Boundary for River Rch & Prof#=Camp Meeting Cre,Reach-1         , 5
Up Type= 0
Dn Type= 3
Dn Slope=0.007
Boundary for River Rch & Prof#=Camp Meeting Cre,Reach-1         , 6
Up Type= 0
Dn Type= 3
Dn Slope=0.007
Boundary for River Rch & Prof#=Camp Meeting Cre,Reach-1         , 7
Up Type= 0
Dn Type= 3
Dn Slope=0.007
DSS Import GetInterval= 0
DSS Import GetPeak= 0
DSS Import FillOption= 0

--- Camp Meeting Creek.g01 (geometry) ---

Geom Title=Existing Conditions
Program Version=4.10

River Reach=Camp Meeting Cre,Reach-1
Reach XY= 30
        1902725.       13917125.       1903235.5      13917723.8
      1903835.17      13917524.5      1906082.06     13917733.97
      1906791.44     13918791.79      1907617.68     13919418.62
      1907676.36     13919971.71      1909249.91     13920225.21
      1910014.31     13920075.77      1910690.27     13920425.53
      1910911.63     13919988.37      1911263.41     13919925.48
      1911376.39     13920171.98      1912219.07     13920127.24
      1914144.25     13920925.62      1915172.45     13919530.73
        1916432.     13920115.84      1917222.58     13919280.54
      1919081.07     13918716.85      1919986.88      13917576.5
      1920754.82     13918275.43      1921477.43     13918119.48
       1922085.5      13917526.2       1924364.5      13917626.2
        1925100.     13918375.41      1925731.07     13918216.87
       1926424.9     13917482.32      1927505.01     13918625.06
      1928115.19     13917485.51        1929575.       13917025.

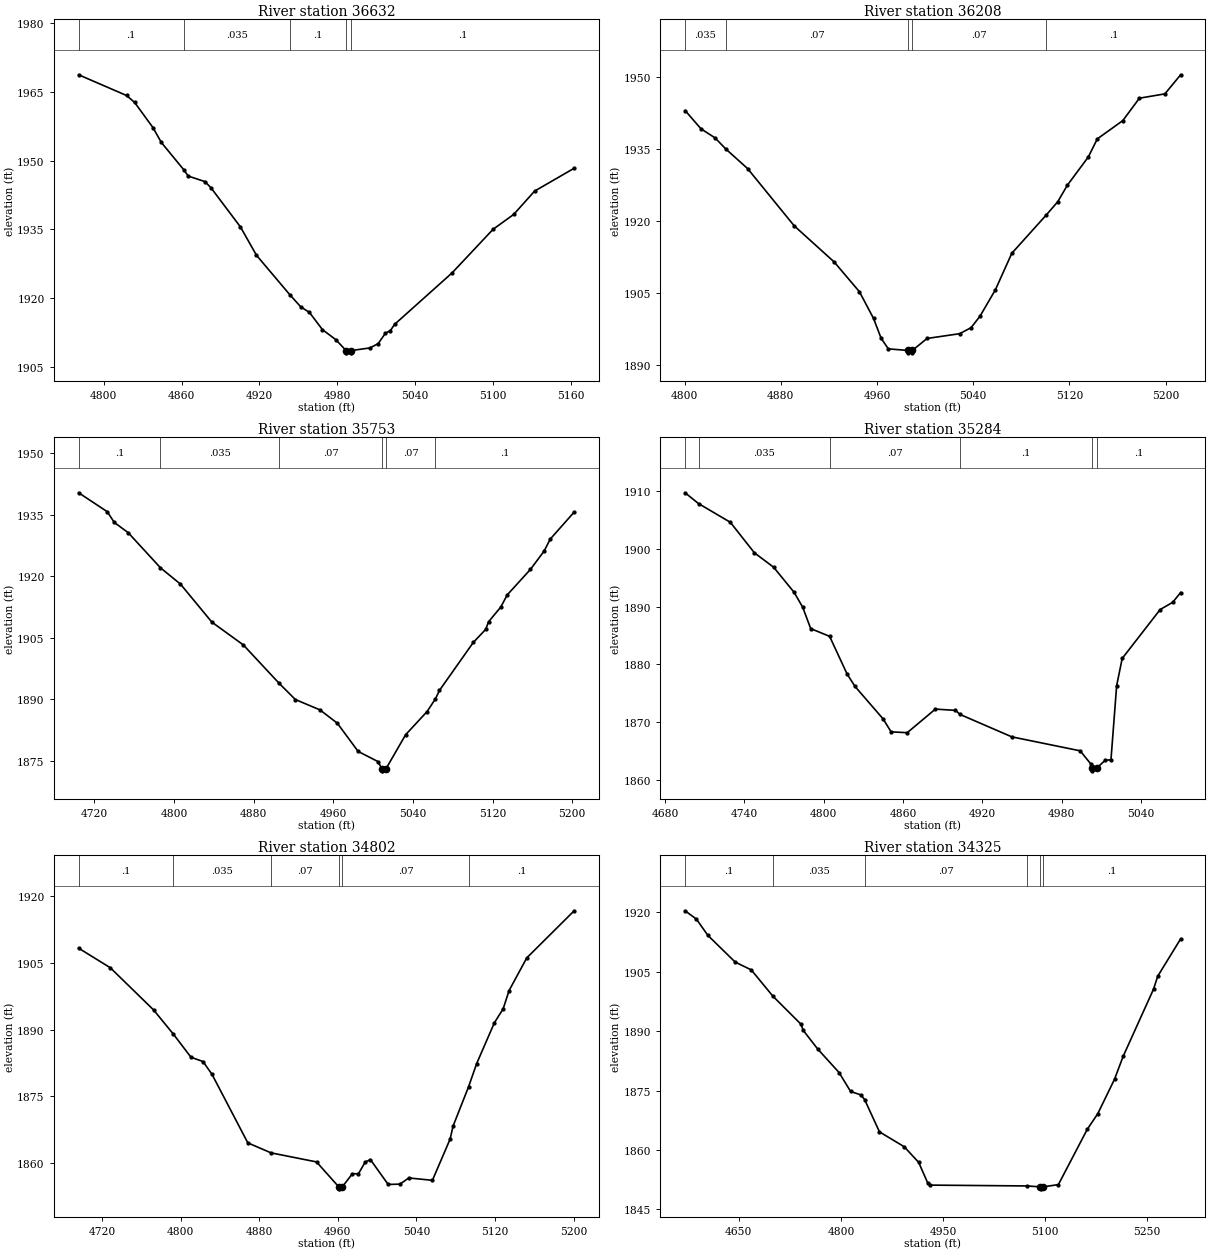
Type RM Length L Ch R = 1 ,36632   ,424,424,424
BEGIN DESCRIPTION:
Camping Meeting Creek 73.0
END DESCRIPTION:
XS GIS Cut Line= 3
        1902625.       13917325.        1902825.       13917225.
      1902874.99     13917075.02
#Sta/Elev= 30
  4780.7 1968.67  4817.6 1964.16  4823.8 1962.66  4837.9 1957.19  4844.4 1953.94
  4861.8 1947.95  4865.1 1946.62    4878 1945.41  4882.6 1944.08  4905.3 1935.56
  4917.7 1929.37  4943.3 1920.81  4951.8 1918.14  4958.5 1916.93  4968.5 1913.18
  4978.8    1911  4986.7 1908.63  4986.9 1908.13  4990.4 1908.13  4990.7 1908.63
  5005.1  1909.2  5011.4 1910.13    5017 1912.39  5020.9 1912.99  5024.1 1914.34
  5068.3 1925.52  5099.9 1935.02  5115.8 1938.26  5131.9 1943.34  5162.4 1948.32
#Mann= 5 ,-1 , 0
  4780.7      .1       0  4861.8    .035       0  4943.3      .1       0
  4986.7     .05       0  4990.7      .1       0
Bank Sta=4986.7,4990.7
XS Rating Curve= 0 ,0
Exp/Cntr=0.3,0.1

Type RM Length L Ch R = 1 ,36208   ,455,455,455
BEGIN DESCRIPTION:
Camping Meeting Creek 72.0
END DESCRIPTION:
XS GIS Cut Line= 3
      1902825.04       13917575.        1903025.       13917575.
        1903175.       13917425.
#Sta/Elev= 30
  4800.4 1942.96  4813.6 1939.16  4825.4 1937.25    4834 1935.02  4852.4 1930.88
  4891.1 1918.99  4924.4 1911.46  4945.4 1905.27  4957.1 1899.73  4963.4 1895.61
  4969.4  1893.4  4985.4 1893.07  4985.6 1892.57  4989.1 1892.57  4989.4 1893.07
  5001.6 1895.56  5028.7 1896.55  5038.2  1897.8  5045.6 1900.17  5058.4 1905.66
  5072.1 1913.27  5100.6 1921.19  5110.3 1923.99  5118.3 1927.43  5135.7 1933.29
  5143.2 1937.06  5164.4 1940.86  5178.2 1945.52  5199.4 1946.42  5212.5 1950.39
#Mann= 5 ,-1 , 0
  4800.4    .035       0    4834     .07       0  4985.4     .05       0
  4989.4     .07       0  5100.6      .1       0
Bank Sta=4985.4,4989.4
XS Rating Curve= 0 ,0
Exp/Cntr=0.3,0.1

Type RM Length L Ch R = 1 ,35753   ,469,469,469
BEGIN DESCRIPTION:
Camping Meeting Creek 71.0
END DESCRIPTION:
XS GIS Cut Line= 3
        1903275.       13917975.        1903425.       13917725.
        1903375.     13917525.01
#Sta/Elev= 30
  4704.3 1940.37  4733.1 1935.75  4740.1 1933.14  4754.1 1930.64  4786.5 1922.08
  4806.6  1918.1  4838.1 1908.84  4869.7 1903.28  4905.7 1893.91    4922 1889.96
  4946.6 1887.45  4964.1  1884.2    4985 1877.32  5004.9 1874.84    5009 1873.08
  5009.3 1872.58    5013 1873.08  5032.7 1881.38  5054.3 1887.04  5062.7 1890.15
  5066.7 1892.19  5100.7 1903.89  5113.1 1907.06    5116 1908.92  5128.4 1912.54
  5134.7 1915.46  5158.1  1921.7  5171.8 1926.15    5178 1929.09    5202 1935.66
#Mann= 6 ,-1 , 0
  4704.3      .1       0  4786.5    .035       0  4905.7     .07       0
    5009     .05       0    5013     .07       0  5062.7      .1       0
Bank Sta=5009,5013
XS Rating Curve= 0 ,0
Exp/Cntr=0.3,0.1

Type RM Length L Ch R = 1 ,35284   ,482,482,482
BEGIN DESCRIPTION:
Camping Meeting Creek 70.0
END DESCRIPTION:
XS GIS Cut Line= 3
        1903775.     13917824.99        1903825.       13917525.
      1903874.97     13917475.03
#Sta/Elev= 30
  4695.2 1909.72  4705.4 1907.84  4729.4 1904.61  4747.6 1899.32  4762.2 1896.81
  4777.6 1892.48  4784.1 1889.91  4790.2 1886.18  4804.5 1884.84  4817.7 1878.32
  4823.7 1876.16    4845 1870.52    4851 1868.29  4863.2 1868.14  4884.5 1872.23
  4899.7 1872.01  4903.2  1871.3  4942.3 1867.42    4994    1865    5002 1862.74
  5002.6 1862.03  5002.9 1861.53  5006.6 1862.03  5013.1 1863.39  5017.3 1863.43
  5021.6 1876.29  5025.8 1881.01  5054.5 1889.48    5064 1890.74    5070 1892.43
#Mann= 6 ,-1 , 0
  4695.2      .1       0  4705.4    .035       0  4804.5     .07       0
  4903.2      .1       0  5002.6     .05       0  5006.6      .1       0
Bank Sta=5002.6,5006.6
XS Rating Curve= 0 ,0
Exp/Cntr=0.3,0.1

Type RM Length L Ch R = 1 ,34802   ,477,477,477
BEGIN DESCRIPTION:
Camping Meeting Creek 69.0
END DESCRIPTION:
XS GIS Cut Line= 3
        1904225.     13917925.01        1904275.       13917625.
        1904275.     13917425.04
#Sta/Elev= 30
  4696.3 1908.34  4728.5 1903.94  4772.6 1894.43  4792.8 1888.96  4810.6 1883.79
  4822.8 1882.83  4831.9 1879.97  4868.4 1864.52    4892 1862.27  4938.3 1860.23
  4960.7 1854.67  4960.9 1854.17  4964.7 1854.67  4974.8 1857.57  4980.9 1857.56
  4987.9 1860.21  4993.1 1860.76  5011.2 1855.16  5023.2 1855.23  5032.2 1856.62
  5056.2 1856.09  5074.2 1865.37  5077.2 1868.29    5093 1877.16  5101.2 1882.36
  5119.2 1891.54  5128.2 1894.71  5134.2 1898.81  5152.2 1906.16  5200.4 1916.76
#Mann= 6 ,-1 , 0
  4696.3      .1       0  4792.8    .035       0    4892     .07       0
  4960.7     .05       0  4964.7     .07       0    5093      .1       0
Bank Sta=4960.7,4964.7
XS Rating Curve= 0 ,0
Exp/Cntr=0.3,0.1

Type RM Length L Ch R = 1 ,34325   ,179,179,179
BEGIN DESCRIPTION:
Camping Meeting Creek 68.0
END DESCRIPTION:
XS GIS Cut Line= 3
      1904324.97     13918025.03        1904625.       13917725.
      1904674.99     13917425.04
#Sta/Elev= 30
    4571 1920.38  4587.6 1918.28  4604.6 1914.15  4644.6 1907.44  4668.2 1905.47
  4700.1 1898.82  4741.3 1891.76  4744.6 1890.21  4765.8 1885.52  4797.3 1879.56
  4814.3 1874.78  4829.5  1873.9  4834.9 1872.73  4856.7 1864.59  4893.1 1860.83
  4914.3  1856.9  4927.9 1851.59  4931.3 1851.15  5073.1 1850.94  5093.4 1850.71
  5093.6 1850.21  5097.4 1850.71  5119.7 1851.28  5162.3 1865.28  5177.5 1869.14
  5202.2 1877.86  5214.9 1883.65  5259.6 1900.62  5265.7 1903.86  5299.4 1913.29
#Mann= 6 ,-1 , 0
    4571      .1       0  4700.1    .035       0  4834.9     .07       0
  5073.1      .1       0  5093.4     .05       0  5097.4      .1       0
Bank Sta=5093.4,5097.4
XS Rating Curve= 0 ,0
Exp/Cntr=0.3,0.1

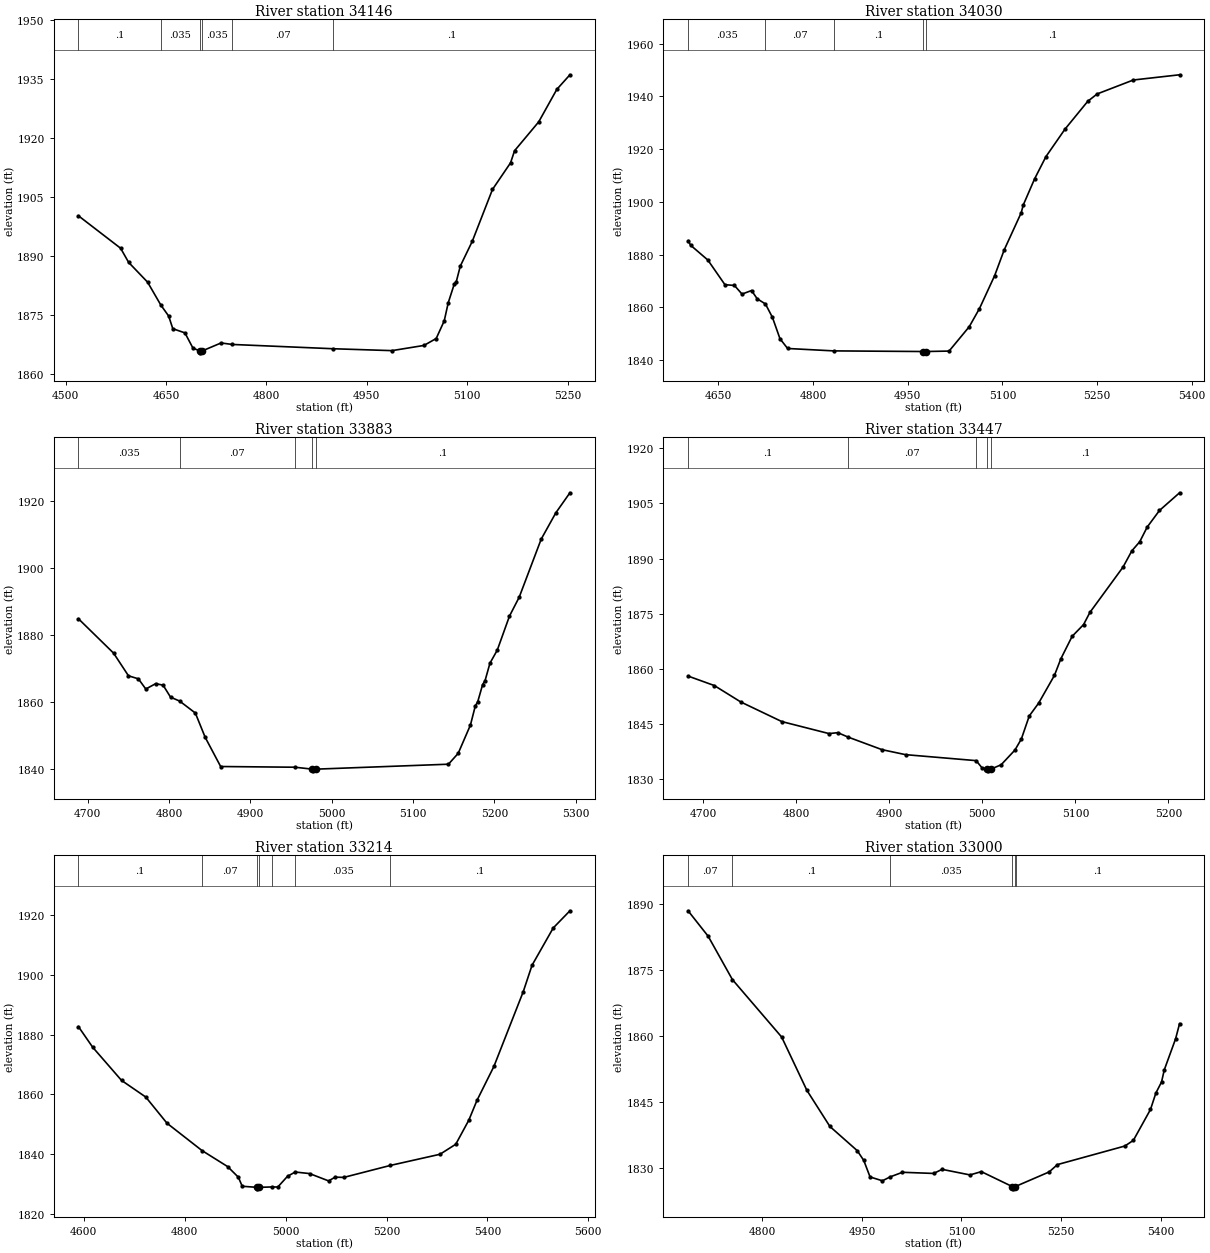
Type RM Length L Ch R = 1 ,34146   ,116,116,116
BEGIN DESCRIPTION:
Camp Meeting Creek 69.1
END DESCRIPTION:
XS GIS Cut Line= 2
      1904776.15     13918076.15      1904741.43     13917342.68
#Sta/Elev= 30
  4519.3 1900.27  4582.3 1892.03  4594.3 1888.44  4622.6 1883.42  4642.4  1877.6
  4654.1 1874.81  4660.3 1871.59  4678.4 1870.53  4690.4 1866.66  4700.4 1865.96
  4700.6 1865.46  4704.4 1865.96  4732.4 1867.97  4749.2 1867.59  4900.1  1866.5
  4987.7 1866.02  5035.5 1867.34  5053.8  1869.1  5065.8 1873.58  5071.8 1878.19
  5080.8 1882.93  5083.8 1883.53  5089.8 1887.49  5107.8 1893.83  5137.9 1906.97
  5164.9 1913.73  5170.9  1916.8    5207 1924.14    5234 1932.38  5253.6 1936.09
#Mann= 6 ,-1 , 0
  4519.3      .1       0  4642.4    .035       0  4700.4     .05       0
  4704.4    .035       0  4749.2     .07       0  4900.1      .1       0
Bank Sta=4700.4,4704.4
XS Rating Curve= 0 ,0
Exp/Cntr=0.3,0.1

Type RM Length L Ch R = 1 ,34030   ,147,147,147
BEGIN DESCRIPTION:
Mapping XS cd45ac80
END DESCRIPTION:
XS GIS Cut Line= 2
      1904896.42      13917972.5      1904830.91     13917196.26
#Sta/Elev= 30
  4601.8 1885.29    4606 1883.56  4633.1    1878  4660.2 1868.65  4675.3 1868.35
  4687.3 1865.08  4702.4 1866.43  4711.4 1863.29  4724.4 1861.35  4735.5 1856.27
  4747.5 1848.15  4759.6 1844.47  4832.5 1843.56  4974.4 1843.32  4974.6 1842.82
  4978.4 1843.32  5015.5 1843.49  5047.5 1852.74  5063.7 1859.62  5087.8 1872.12
  5102.8  1881.8  5129.9 1895.94  5132.9 1898.75    5151 1908.73    5169 1917.17
  5199.1 1927.55  5235.3 1938.14  5250.3 1940.93  5307.5  1946.2  5380.8 1948.18
#Mann= 5 ,-1 , 0
  4601.8    .035       0  4724.4     .07       0  4832.5      .1       0
  4974.4     .05       0  4978.4      .1       0
Bank Sta=4974.4,4978.4
XS Rating Curve= 0 ,0
Exp/Cntr=0.3,0.1

Type RM Length L Ch R = 1 ,33883   ,436,436,436
BEGIN DESCRIPTION:
Camping Meeting Creek 67.0
END DESCRIPTION:
XS GIS Cut Line= 3
      1904925.01     13917974.97        1904975.       13917675.
        1904975.       13917375.
#Sta/Elev= 30
  4688.8 1884.85    4732 1874.59  4750.3 1867.82  4762.5 1866.91  4771.6 1863.87
  4783.8 1865.48  4792.9 1865.01    4802 1861.45  4813.2 1860.27  4832.5  1856.7
  4844.6 1849.44  4863.6 1840.73    4955 1840.52  4976.4 1839.94  4976.7 1839.44
  4980.4 1839.94  5143.6 1841.42  5155.6 1844.68  5170.6 1853.11  5176.6 1858.82
  5179.6 1860.09  5185.6  1865.2  5188.6 1866.39  5194.6 1871.59  5203.6 1875.49
  5218.6 1885.65  5230.6 1891.32  5257.6 1908.64  5275.6  1916.5  5292.9 1922.47
#Mann= 5 ,-1 , 0
  4688.8    .035       0  4813.2     .07       0    4955      .1       0
  4976.4     .05       0  4980.4      .1       0
Bank Sta=4976.4,4980.4
XS Rating Curve= 0 ,0
Exp/Cntr=0.3,0.1

Type RM Length L Ch R = 1 ,33447   ,233,233,233
BEGIN DESCRIPTION:
Camping Meeting Creek 66.0
END DESCRIPTION:
XS GIS Cut Line= 3
      1905274.99     13917875.04        1905375.       13917575.
        1905225.       13917425.
#Sta/Elev= 30
  4683.6 1857.97  4711.8 1855.39  4740.3 1850.91  4784.4 1845.57  4835.1  1842.3
  4844.6 1842.55  4855.7 1841.34  4892.1 1837.92  4917.4 1836.56  4993.3 1834.93
  4999.6 1832.97  5005.5 1832.65  5005.7 1832.15  5009.5 1832.65  5020.2 1833.81
    5035 1837.81  5041.9 1840.82  5050.4  1847.1  5060.5  1850.6  5077.5 1858.17
  5084.3 1862.64  5096.5  1868.8  5108.8    1872  5115.6 1875.31  5151.2 1887.66
  5160.7 1892.09  5169.2 1894.58  5177.2 1898.57  5190.4 1903.09    5212 1907.91
#Mann= 5 ,-1 , 0
  4683.6      .1       0  4855.7     .07       0  4993.3      .1       0
  5005.5     .05       0  5009.5      .1       0
Bank Sta=5005.5,5009.5
XS Rating Curve= 0 ,0
Exp/Cntr=0.3,0.1

Type RM Length L Ch R = 1 ,33214   ,214,214,214
BEGIN DESCRIPTION:
Mapping XS 95b3d5ba
END DESCRIPTION:
XS GIS Cut Line= 3
      1905539.78      13918038.5       1905563.3     13917665.84
      1905983.71     13917236.64
#Sta/Elev= 30
  4589.3 1882.65  4617.6 1875.75  4674.7 1864.68  4722.8 1859.11  4764.9 1850.36
  4834.1 1841.25  4885.1 1835.87  4906.2 1832.34    4914  1829.3  4943.2 1828.94
  4943.5 1828.44  4947.2 1828.94  4972.3 1829.07  4984.5 1829.05  5003.7 1832.63
    5019 1834.06  5047.5 1833.54  5085.2 1831.09  5098.1 1832.35  5115.2 1832.26
  5207.5 1836.26  5305.9 1839.99  5337.2 1843.34  5363.1 1851.39  5379.2 1857.98
  5412.8 1869.34    5471 1894.34  5488.4 1903.16  5530.4 1915.62  5563.5 1921.36
#Mann= 7 ,-1 , 0
  4589.3      .1       0  4834.1     .07       0  4943.2     .05       0
  4947.2     .07       0  4972.3      .1       0    5019    .035       0
  5207.5      .1       0
Bank Sta=4943.2,4947.2
XS Rating Curve= 0 ,0
Exp/Cntr=0.3,0.1

Type RM Length L Ch R = 1 ,33000   ,472,472,472
BEGIN DESCRIPTION:
Camping Meeting Creek 65.0
END DESCRIPTION:
XS GIS Cut Line= 3
      1905624.99     13918075.04        1905725.       13917775.
      1906024.98     13917475.02
#Sta/Elev= 30
  4688.1 1888.44  4718.4 1882.65  4754.9  1872.8  4829.1 1859.75  4867.1 1847.64
  4901.8 1839.42  4942.9 1833.94  4952.8 1831.71  4962.3 1827.95  4980.9 1827.08
  4992.8 1827.98  5011.1 1829.01  5058.1 1828.75  5070.8 1829.68  5112.9 1828.41
  5129.9 1829.16  5176.8 1825.75  5177.1 1825.25  5180.8 1825.75  5182.8 1825.88
  5232.1 1829.09  5244.6 1830.76  5346.2 1834.98    5359 1836.27  5384.8 1843.29
  5392.9 1847.02  5401.4 1849.52  5405.6  1852.3  5422.6 1859.34  5428.6 1862.79
#Mann= 6 ,-1 , 0
  4688.1     .07       0  4754.9      .1       0  4992.8    .035       0
  5176.8    .035       0  5180.8    .035       0  5182.8      .1       0
Bank Sta=5176.8,5180.8
XS Rating Curve= 0 ,0
Exp/Cntr=0.3,0.1

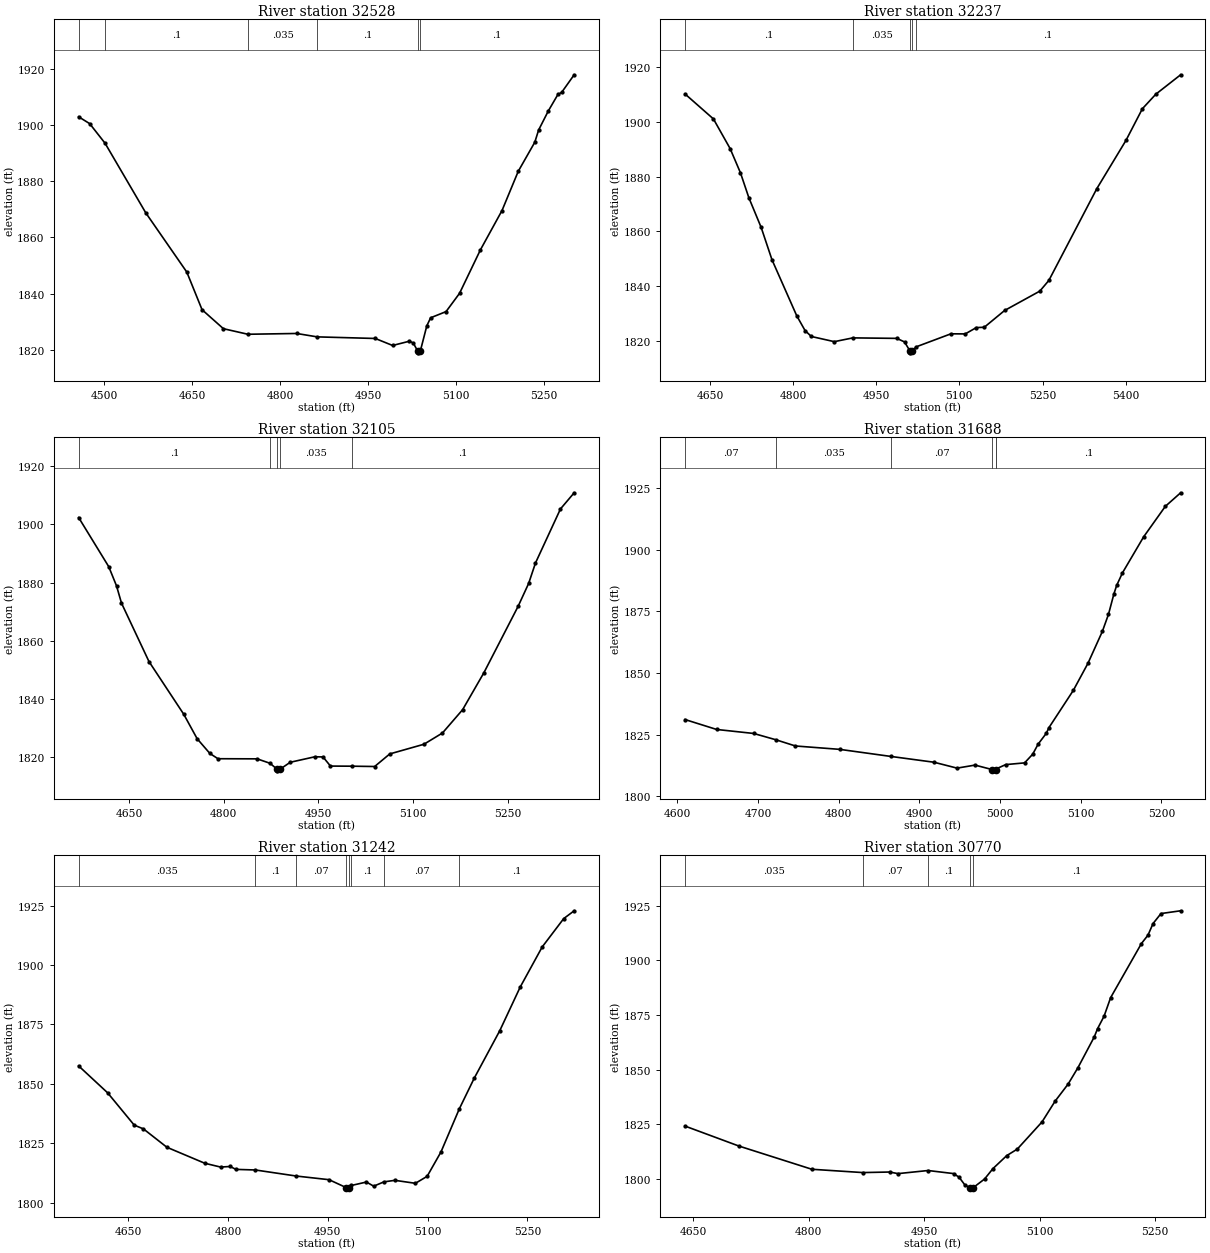
Type RM Length L Ch R = 1 ,32528   ,291,291,291
BEGIN DESCRIPTION:
Camping Meeting Creek 64.0
END DESCRIPTION:
XS GIS Cut Line= 3
      1905788.23     13918193.65      1906099.09     13917755.81
      1906224.99     13917475.02
#Sta/Elev= 30
  4456.7  1902.9  4475.5 1900.47  4501.7 1893.51  4571.2 1868.71  4641.1 1847.65
  4667.1 1834.26  4703.5 1827.51  4745.2 1825.53  4828.3 1825.81  4863.4  1824.6
  4962.4 1824.03  4991.9 1821.54  5020.6 1823.06  5027.1 1822.43    5035 1819.42
  5035.3 1818.92    5039 1819.42  5050.2 1828.52  5056.7 1831.39    5083 1833.59
    5106 1840.09  5141.6 1855.57  5178.4 1869.55  5206.1 1883.52  5234.3 1893.86
  5240.8  1898.2  5257.4 1905.01  5273.7 1910.85    5280 1911.57  5301.4 1917.85
#Mann= 6 ,-1 , 0
  4456.7     .07       0  4501.7      .1       0  4745.2    .035       0
  4863.4      .1       0    5035     .05       0    5039      .1       0
Bank Sta=5035,5039
XS Rating Curve= 0 ,0
Exp/Cntr=0.3,0.1

Type RM Length L Ch R = 1 ,32237   ,132,132,132
BEGIN DESCRIPTION:
Mapping XS f2c63ad0
END DESCRIPTION:
XS GIS Cut Line= 2
      1905818.22     13918269.61      1906531.75     13917731.33
#Sta/Elev= 30
  4605.3 1910.24  4656.4 1901.13  4686.5 1890.29  4705.2  1881.4  4720.3 1872.31
  4742.5 1861.45    4762 1849.63  4806.7 1829.12  4821.7 1823.72    4833 1821.56
  4874.4 1819.67  4907.9 1821.05  4987.1 1820.87  5001.1 1819.57  5011.4 1816.08
  5011.6 1815.58  5015.4 1816.08  5021.6 1817.74  5084.8 1822.54  5110.6  1822.5
  5130.6 1824.82  5144.9 1824.93  5181.6 1831.07  5245.1 1838.15  5261.4 1842.06
  5347.9 1875.63  5400.5 1893.28  5430.1 1904.86  5454.4 1910.19  5499.1 1917.28
#Mann= 5 ,-1 , 0
  4605.3      .1       0  4907.9    .035       0  5011.4    .035       0
  5015.4    .035       0  5021.6      .1       0
Bank Sta=5011.4,5015.4
XS Rating Curve= 0 ,0
Exp/Cntr=0.3,0.1

Type RM Length L Ch R = 1 ,32105   ,417,417,417
BEGIN DESCRIPTION:
Camping Meeting Creek 63.0
END DESCRIPTION:
XS GIS Cut Line= 3
      1905924.98     13918425.02        1906225.       13918125.
      1906525.04     13917924.97
#Sta/Elev= 30
  4570.3 1902.39    4618 1885.47  4630.3 1878.87  4638.2 1872.92  4681.7 1852.82
  4736.8 1834.66    4758 1826.24  4778.2 1821.16    4791 1819.35    4853 1819.31
  4873.5 1817.78  4884.9 1815.68  4885.2 1815.18  4888.9 1815.68  4905.5 1818.13
  4944.7 1820.03  4957.4 1819.96  4969.2 1816.82  5003.5 1816.78  5039.2 1816.67
  5063.1    1821  5117.2 1824.33  5146.6 1828.21  5178.5 1836.23  5212.2 1848.95
  5266.3 1871.77  5283.1  1879.7  5293.9 1886.73  5333.5 1905.35  5355.2 1910.91
#Mann= 5 ,-1 , 0
  4570.3      .1       0  4873.5    .035       0  4884.9    .035       0
  4888.9    .035       0  5003.5      .1       0
Bank Sta=4884.9,4888.9
XS Rating Curve= 0 ,0
Exp/Cntr=0.3,0.1

Type RM Length L Ch R = 1 ,31688   ,446,446,446
BEGIN DESCRIPTION:
Camping Meeting Creek 62.0
END DESCRIPTION:
XS GIS Cut Line= 3
      1906224.98     13918625.01        1906525.       13918375.
      1906724.96     13918275.02
#Sta/Elev= 30
  4609.7 1831.11  4648.8 1827.09  4694.7 1825.47  4722.3  1822.9  4746.4 1820.39
  4801.2 1819.02  4865.3 1816.12  4918.2 1813.79  4946.7  1811.4    4969 1812.63
  4990.4  1810.8  4990.7  1810.3  4994.4  1810.8    4995 1811.07    5007 1812.83
  5030.4 1813.53  5040.5 1817.07  5047.2 1821.14  5057.3 1825.53  5060.6 1827.84
  5090.8 1842.95  5108.9 1853.91  5126.8 1866.89  5134.4 1873.83  5141.1  1882.1
  5144.5 1885.53  5151.7 1890.65    5178 1905.29  5204.8 1917.63  5223.8 1923.15
#Mann= 6 ,-1 , 0
  4609.7     .07       0  4722.3    .035       0  4865.3     .07       0
  4990.4     .05       0  4994.4     .07       0    4995      .1       0
Bank Sta=4990.4,4994.4
XS Rating Curve= 0 ,0
Exp/Cntr=0.3,0.1

Type RM Length L Ch R = 1 ,31242   ,472,472,472
BEGIN DESCRIPTION:
Camping Meeting Creek 61.0
END DESCRIPTION:
XS GIS Cut Line= 3
        1906475.       13919025.        1906775.       13918725.
      1906974.98     13918475.02
#Sta/Elev= 30
  4575.8 1857.55  4619.3 1846.24  4659.3 1832.63  4673.2 1831.02  4708.4  1823.3
  4765.3 1816.57    4789 1814.97  4803.5 1815.21    4812 1813.99  4841.3 1813.74
    4903 1811.18    4952 1809.65  4977.9  1806.3  4978.1  1805.8  4981.9  1806.3
  4985.4 1807.21  5008.1 1808.66  5019.1 1806.92  5034.4 1808.74  5050.9 1809.38
  5081.7 1808.13  5099.3 1811.06  5120.1 1821.32  5147.7  1839.5    5170 1852.35
  5208.5 1872.41  5239.2 1890.79  5272.2 1907.65  5304.5 1919.57  5320.2 1922.86
#Mann= 8 ,-1 , 0
  4575.8    .035       0  4841.3      .1       0    4903     .07       0
  4977.9     .05       0  4981.9     .07       0  4985.4      .1       0
  5034.4     .07       0  5147.7      .1       0
Bank Sta=4977.9,4981.9
XS Rating Curve= 0 ,0
Exp/Cntr=0.3,0.1

Type RM Length L Ch R = 1 ,30770   ,444,444,444
BEGIN DESCRIPTION:
Camping Meeting Creek 60.0
END DESCRIPTION:
XS GIS Cut Line= 3
      1906775.02     13919224.99        1907075.       13919025.
      1907275.02     13918824.98
#Sta/Elev= 30
  4639.7 1824.18  4709.5 1815.07  4804.3 1804.44  4870.4 1802.93  4905.3 1803.18
  4916.1 1802.45  4955.2 1803.87  4988.2 1802.47  4995.4 1800.82  5003.1  1797.2
  5009.6 1795.99  5009.8 1795.49  5013.6 1795.99  5028.5 1799.97  5039.4 1804.74
  5057.3 1810.68    5071 1813.66  5103.1 1826.08  5120.1 1835.58    5137  1843.4
  5149.8 1850.92    5171    1865  5175.2 1868.72  5183.7 1874.46  5192.2 1882.93
  5232.2 1907.68  5240.7 1911.51  5247.3 1916.83  5257.6 1921.39  5283.1 1922.66
#Mann= 5 ,-1 , 0
  4639.7    .035       0  4870.4     .07       0  4955.2      .1       0
  5009.6     .05       0  5013.6      .1       0
Bank Sta=5009.6,5013.6
XS Rating Curve= 0 ,0
Exp/Cntr=0.3,0.1

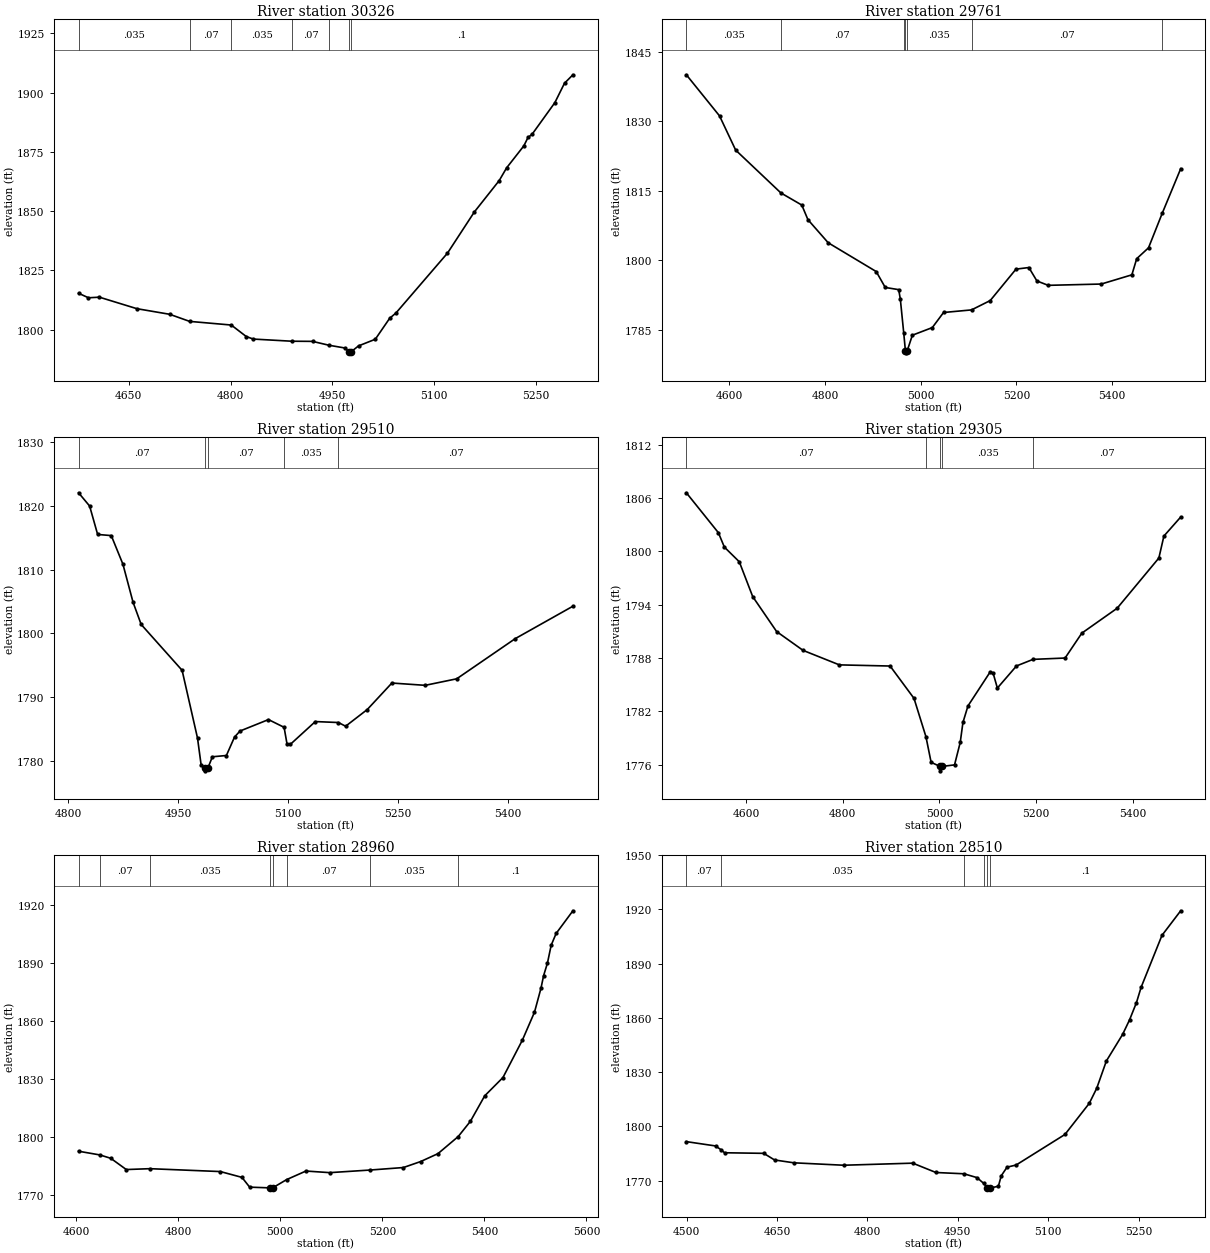
Type RM Length L Ch R = 1 ,30326   ,565,565,565
BEGIN DESCRIPTION:
Camping Meeting Creek 59.0
END DESCRIPTION:
XS GIS Cut Line= 3
      1907075.01     13919624.99        1907375.       13919325.
        1907425.     13919024.98
#Sta/Elev= 30
    4576 1815.39  4590.6 1813.49  4606.7 1813.74  4661.9 1808.89  4710.3 1806.52
  4739.6 1803.53    4801 1801.99  4823.1 1797.14  4833.4 1796.07  4890.4 1795.16
  4920.7  1795.1    4945 1793.46  4969.1 1792.27  4973.8 1790.76  4974.1 1790.26
  4977.8 1790.76  4988.5 1793.19  5013.2 1795.99  5034.4 1804.84  5043.6 1807.05
  5119.6 1832.33  5159.1 1849.67  5195.8 1862.94  5206.7  1868.3  5232.1 1877.58
  5238.2 1881.11  5244.3 1882.49  5277.8 1895.82    5292 1904.01  5304.4 1907.57
#Mann= 7 ,-1 , 0
    4576    .035       0  4739.6     .07       0    4801    .035       0
  4890.4     .07       0    4945      .1       0  4973.8     .05       0
  4977.8      .1       0
Bank Sta=4973.8,4977.8
XS Rating Curve= 0 ,0
Exp/Cntr=0.3,0.1

Type RM Length L Ch R = 1 ,29761   ,251,251,251
BEGIN DESCRIPTION:
Camping Meeting Creek 58.0
END DESCRIPTION:
XS GIS Cut Line= 3
      1907007.97     13919795.84      1907487.24     13919642.17
      1907960.03     13919401.77
#Sta/Elev= 30
    4510 1840.06  4579.4 1831.17  4613.1 1823.78  4707.7 1814.52  4751.4  1811.9
  4764.2 1808.75  4806.6 1803.75    4907 1797.53  4925.9 1794.09    4954 1793.62
  4957.4 1791.62  4964.6 1784.21    4968 1780.46  4968.3 1779.96    4972 1780.46
  4982.6 1783.77  5024.3 1785.42  5047.8 1788.68  5106.3 1789.24  5145.4 1791.26
  5199.3 1798.05  5226.2  1798.4    5243  1795.5  5266.6 1794.55  5377.6 1794.83
  5441.6 1796.82  5451.7 1800.31  5476.4 1802.66  5505.1 1810.13  5543.7 1819.76
#Mann= 7 ,-1 , 0
    4510    .035       0  4707.7     .07       0  4964.6    .035       0
    4968    .035       0    4972    .035       0  5106.3     .07       0
  5505.1      .1       0
Bank Sta=4968,4972
XS Rating Curve= 0 ,0
Exp/Cntr=0.3,0.1

Type RM Length L Ch R = 1 ,29510   ,205,205,205
BEGIN DESCRIPTION:
Camping Meeting Creek 57.0
END DESCRIPTION:
XS GIS Cut Line= 3
      1907425.03     13919974.98      1907590.22     13919854.21
      1907925.03     13919524.97
#Sta/Elev= 30
    4814 1822.01  4829.1 1819.93    4840 1815.49  4858.6 1815.31  4874.5 1810.83
  4888.3 1804.88  4899.4  1801.4  4955.2 1794.23  4976.2 1783.63  4981.2 1779.38
  4986.6    1779  4986.9  1778.5  4990.6    1779  4996.5  1780.7  5015.6  1780.9
  5026.7 1783.79  5034.2 1784.73    5073 1786.52  5094.3 1785.31  5098.4 1782.63
  5102.7 1782.63  5136.9 1786.21  5168.4 1786.06  5178.2 1785.48  5207.7 1788.09
  5241.3 1792.24  5286.7 1791.88  5329.7  1792.9  5409.6 1799.19  5488.2 1804.26
#Mann= 5 ,-1 , 0
    4814     .07       0  4986.6     .05       0  4990.6     .07       0
  5094.3    .035       0  5168.4     .07       0
Bank Sta=4986.6,4990.6
XS Rating Curve= 0 ,0
Exp/Cntr=0.3,0.1

Type RM Length L Ch R = 1 ,29305   ,345,345,345
BEGIN DESCRIPTION:
Mapping XS 02d226bd
END DESCRIPTION:
XS GIS Cut Line= 3
      1907812.84     13920480.58      1907693.06     13920001.44
      1907958.67     13919543.13
#Sta/Elev= 30
    4476  1806.6  4542.3 1802.11  4554.7 1800.49  4585.6 1798.84  4613.4 1794.92
  4662.9 1790.99  4717.7 1788.87  4792.8 1787.24  4897.9 1787.11  4947.4 1783.47
  4972.1 1779.16  4982.8 1776.28  5001.1 1775.82  5001.5 1775.32  5006.1 1775.82
  5031.3 1775.99  5043.1 1778.52  5048.7 1780.76  5059.1 1782.62  5105.4 1786.47
  5111.1 1786.33    5120 1784.63  5159.6 1787.12  5193.9 1787.86  5260.2 1788.01
  5294.9 1790.81    5368 1793.61  5454.4 1799.26  5464.8 1801.73  5499.6 1803.87
#Mann= 5 ,-1 , 0
    4476     .07       0  4972.1    .035       0  5001.1    .035       0
  5006.1    .035       0  5193.9     .07       0
Bank Sta=5001.1,5006.1
XS Rating Curve= 0 ,0
Exp/Cntr=0.3,0.1

Type RM Length L Ch R = 1 ,28960   ,450,450,450
BEGIN DESCRIPTION:
Camping Meeting Creek 56.0
END DESCRIPTION:
XS GIS Cut Line= 3
        1907975.     13920275.03        1908025.       13919875.
      1908424.98     13919475.02
#Sta/Elev= 30
  4604.6 1792.66  4646.4 1790.74  4667.7    1789  4698.1 1783.18  4744.4 1783.63
  4882.5 1782.14  4924.8 1779.13  4939.9 1774.07  4979.9  1773.7  4980.3  1773.2
  4984.9  1773.7  5012.2 1777.96  5050.2 1782.41  5096.9 1781.58  5176.5 1782.94
  5241.1 1784.22    5275 1787.32    5309 1791.42  5348.6 1800.25  5372.6 1808.19
  5400.5 1821.31  5436.3  1830.8  5474.4 1850.17  5498.1 1864.61  5510.8 1876.99
    5516 1883.54  5523.5 1890.04  5530.8 1899.25  5540.5 1905.33  5573.4 1917.07
#Mann= 8 ,-1 , 0
  4604.6    .035       0  4646.4     .07       0  4744.4    .035       0
  4979.9    .035       0  4984.9    .035       0  5012.2     .07       0
  5176.5    .035       0  5348.6      .1       0
Bank Sta=4979.9,4984.9
XS Rating Curve= 0 ,0
Exp/Cntr=0.3,0.1

Type RM Length L Ch R = 1 ,28510   ,468,468,468
BEGIN DESCRIPTION:
Camping Meeting Creek 55.0
END DESCRIPTION:
XS GIS Cut Line= 3
      1908124.98     13920325.02        1908425.       13919925.
      1908625.01     13919674.99
#Sta/Elev= 30
  4499.7 1791.54  4548.1 1789.15  4556.8 1787.15  4563.1 1785.38  4628.1 1785.06
    4646  1781.4  4678.1 1779.82  4760.6 1778.48  4875.3 1779.63  4913.8 1774.46
  4960.3 1773.75  4981.9 1771.63  4993.1 1768.42  4999.2 1765.92  4999.5 1765.42
  5004.2 1765.92  5017.4 1766.85  5022.2 1772.66  5031.8 1777.42  5046.8 1778.59
  5127.8 1795.49  5168.2 1812.72  5180.6 1821.08  5196.6 1836.18  5223.5 1850.84
    5235 1858.87  5246.5 1868.45  5254.2  1876.9  5288.8 1905.65  5319.9 1919.26
#Mann= 6 ,-1 , 0
  4499.7     .07       0  4556.8    .035       0  4960.3     .07       0
  4993.1      .1       0  4999.2     .05       0  5004.2      .1       0
Bank Sta=4999.2,5004.2
XS Rating Curve= 0 ,0
Exp/Cntr=0.3,0.1

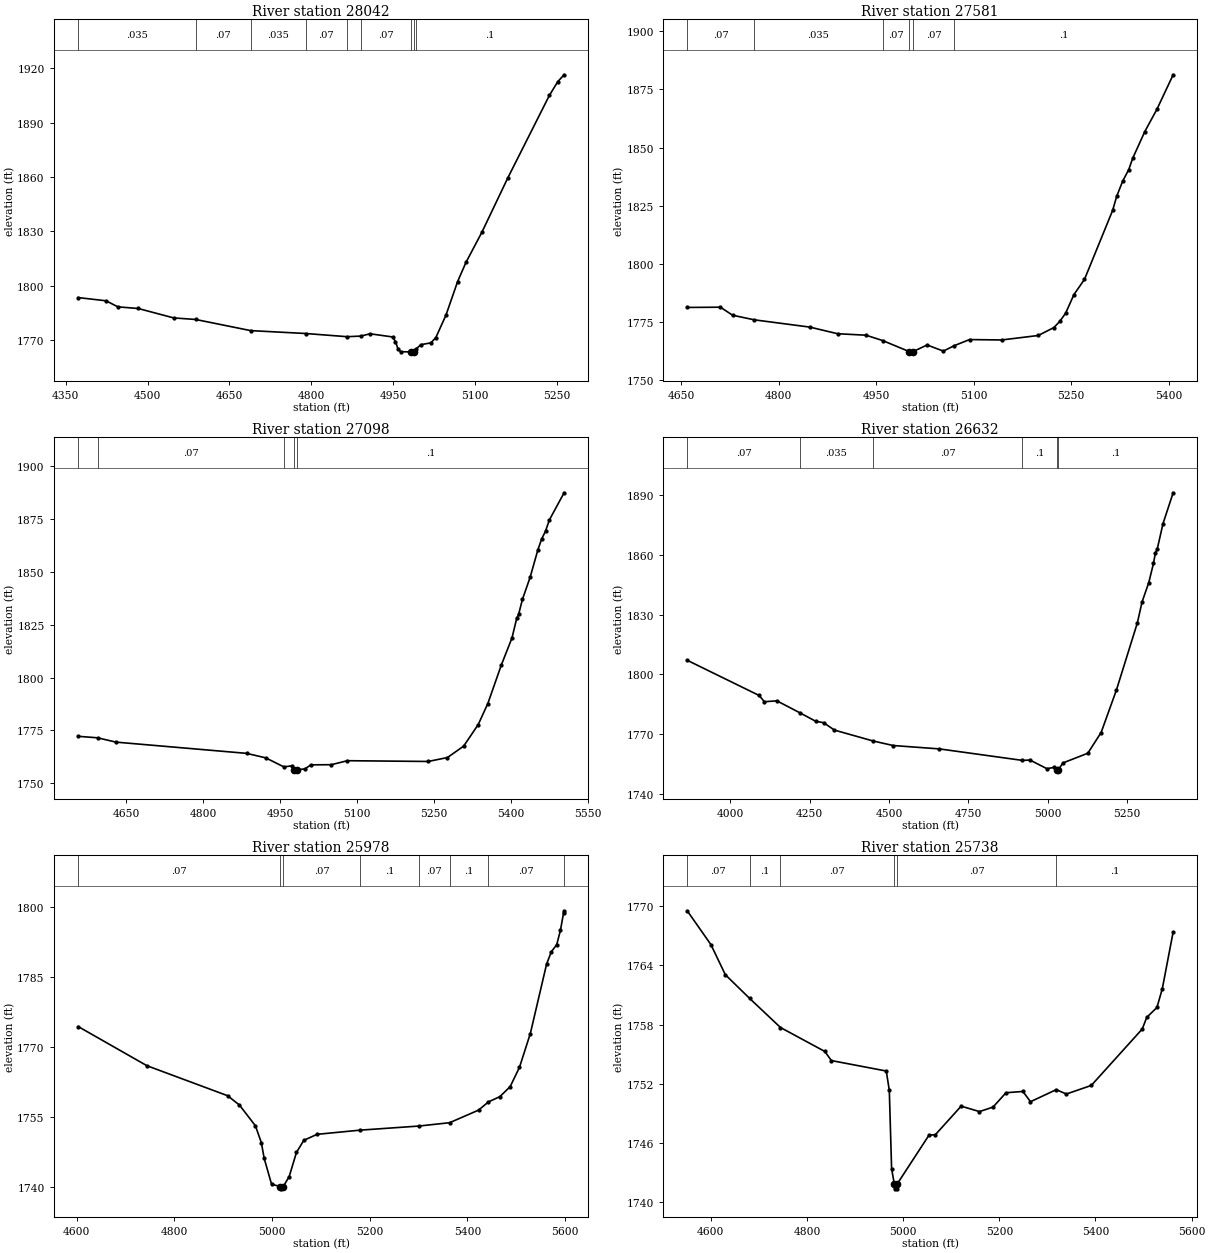
Type RM Length L Ch R = 1 ,28042   ,461,461,461
BEGIN DESCRIPTION:
Camping Meeting Creek 54.0
END DESCRIPTION:
XS GIS Cut Line= 3
       1908664.8     13920639.75        1908825.       13920025.
      1908874.99     13919775.03
#Sta/Elev= 30
  4372.9 1793.41    4424 1791.63  4445.7 1788.28  4482.9 1787.38    4548 1782.17
    4588 1781.32  4688.9 1775.16  4789.7 1773.56  4865.6  1771.8  4890.5 1772.13
  4907.7  1773.4  4948.9 1771.66  4954.2 1769.13  4958.8 1765.06  4963.5 1763.53
  4982.6 1763.38    4983 1762.88  4987.7 1763.38  4991.3 1764.83  5000.7 1767.39
  5019.1 1768.39  5028.2 1771.34  5046.7  1783.7  5068.1 1802.29  5083.4 1812.88
  5112.5 1829.49  5159.9 1859.46  5236.3 1905.18  5251.6 1912.73  5263.1 1916.49
#Mann= 9 ,-1 , 0
  4372.9    .035       0    4588     .07       0  4688.9    .035       0
  4789.7     .07       0  4865.6    .035       0  4890.5     .07       0
  4982.6     .05       0  4987.7     .07       0  4991.3      .1       0
Bank Sta=4982.6,4987.7
XS Rating Curve= 0 ,0
Exp/Cntr=0.3,0.1

Type RM Length L Ch R = 1 ,27581   ,483,483,483
BEGIN DESCRIPTION:
Camping Meeting Creek 53.0
END DESCRIPTION:
XS GIS Cut Line= 3
      1909075.02     13920524.96        1909225.       13920225.
      1909124.99     13919824.97
#Sta/Elev= 30
  4659.3 1781.35  4710.4 1781.46  4729.1 1778.01  4762.3 1776.04  4847.9 1772.91
  4890.7 1770.06  4934.3 1769.43  4959.8 1767.15  5001.3 1762.35  5001.7 1761.85
  5006.5 1762.35  5028.5 1765.23  5053.4 1762.59  5069.9  1764.9  5093.7 1767.55
  5143.1 1767.38  5199.4  1769.3  5223.5 1772.71  5232.8 1775.44  5241.6 1778.91
  5254.4  1786.9  5270.6 1793.42  5313.9 1823.05  5320.1 1829.05  5329.2 1835.52
  5338.7 1840.59  5344.8 1845.45  5363.4  1856.9    5382 1866.46    5407  1881.3
#Mann= 6 ,-1 , 0
  4659.3     .07       0  4762.3    .035       0  4959.8     .07       0
  5001.3     .05       0  5006.5     .07       0  5069.9      .1       0
Bank Sta=5001.3,5006.5
XS Rating Curve= 0 ,0
Exp/Cntr=0.3,0.1

Type RM Length L Ch R = 1 ,27098   ,466,466,466
BEGIN DESCRIPTION:
Camping Meeting Creek 52.0
END DESCRIPTION:
XS GIS Cut Line= 3
        1909475.       13920525.        1909675.       13920125.
      1909974.99     13919725.01
#Sta/Elev= 30
  4556.6 1772.23  4594.4 1771.52  4630.4 1769.48  4884.9 1764.17  4922.2 1762.05
  4957.6 1757.78  4972.6 1758.26  4977.2 1756.41  4977.6 1755.91  4982.4 1756.41
  4998.9 1756.83  5010.1 1758.74  5050.1 1758.81  5081.4  1760.7  5238.9 1760.34
  5276.4 1762.19    5308 1767.58  5336.4 1777.77  5355.1 1787.68  5381.4 1805.88
  5402.3 1818.75  5411.4 1827.94  5415.1 1829.81  5422.6 1836.95  5437.6 1847.38
  5452.6 1860.25  5460.1 1865.51  5467.6 1869.18  5475.1 1874.48  5503.8 1887.32
#Mann= 5 ,-1 , 0
  4556.6    .035       0  4594.4     .07       0  4957.6      .1       0
  4977.2     .05       0  4982.4      .1       0
Bank Sta=4977.2,4982.4
XS Rating Curve= 0 ,0
Exp/Cntr=0.3,0.1

Type RM Length L Ch R = 1 ,26632   ,654,654,654
BEGIN DESCRIPTION:
Camping Meeting Creek 51.0
END DESCRIPTION:
XS GIS Cut Line= 3
      1909274.98     13920925.02        1910075.       13920125.
        1910075.       13919725.
#Sta/Elev= 30
    3864 1807.03  4090.4 1789.37  4107.3 1786.21  4146.6 1786.65  4218.8 1780.66
  4268.6 1776.42    4294 1775.66    4328 1771.95  4449.8 1766.48    4513  1764.2
  4658.9  1762.5  4920.4 1756.73  4944.2  1756.9  4997.6 1752.56  5018.4 1753.17
  5027.8 1751.98  5028.2 1751.48  5033.1 1751.98  5048.4 1755.47  5126.4 1760.32
  5168.4 1770.73  5216.4 1791.96  5282.6 1825.81  5297.4 1836.33  5318.6 1846.08
  5333.4  1855.7  5339.4 1860.88  5345.6 1863.13  5363.4 1875.67  5395.4 1891.19
#Mann= 6 ,-1 , 0
    3864     .07       0  4218.8    .035       0  4449.8     .07       0
  4920.4      .1       0  5027.8     .05       0  5033.1      .1       0
Bank Sta=5027.8,5033.1
XS Rating Curve= 0 ,0
Exp/Cntr=0.3,0.1

Type RM Length L Ch R = 1 ,25978   ,240,240,240
BEGIN DESCRIPTION:
Mapping XS f6310270
END DESCRIPTION:
XS GIS Cut Line= 4
      1910557.29     13920821.71      1910554.69     13920431.13
      1910549.48     13920273.58      1910274.75     13919922.02
#Sta/Elev= 30
  4603.3 1774.41  4744.1 1765.99  4909.1 1759.55  4933.4 1757.54  4966.1 1753.08
  4978.1 1749.49    4984 1746.08  4999.1 1740.52  5017.1 1740.04  5017.6 1739.54
  5023.1 1740.04  5035.1 1742.17  5050.1 1747.38  5065.1 1749.96  5092.1 1751.25
  5180.3 1752.15  5300.6 1753.03  5363.5 1753.75  5422.6 1756.45  5442.8 1758.21
  5466.6 1759.37  5487.4 1761.51  5506.4 1765.65  5528.6  1772.9  5561.9 1787.83
  5571.6 1790.48  5582.6    1792  5590.2 1795.06  5596.6  1798.8  5597.7 1799.28
#Mann= 8 ,-1 , 0
  4603.3     .07       0  5017.1     .05       0  5023.1     .07       0
  5180.3      .1       0  5300.6     .07       0  5363.5      .1       0
  5442.8     .07       0  5596.6      .1       0
Bank Sta=5017.1,5023.1
XS Rating Curve= 0 ,0
Exp/Cntr=0.3,0.1

Type RM Length L Ch R = 1 ,25738   ,405,405,405
BEGIN DESCRIPTION:
Camping Meeting Creek 50.0
END DESCRIPTION:
XS GIS Cut Line= 4
      1910844.87     13920793.21      1910840.75     13920442.63
        1910775.       13920375.      1910375.01     13919975.01
#Sta/Elev= 30
  4550.9 1769.54  4600.1 1766.12  4630.2 1763.06  4680.7 1760.66  4744.9 1757.71
  4837.2 1755.28  4850.7 1754.36  4964.9  1753.3  4971.2 1751.34    4976 1743.38
  4981.6 1741.86  4982.1 1741.36  4987.2 1741.36  4987.7 1741.86    5054 1746.82
  5066.7 1746.83  5120.6 1749.74  5158.7 1749.19  5186.8 1749.64  5213.9  1751.1
  5249.1 1751.23  5264.8 1750.19  5318.3 1751.41  5339.5 1750.97  5391.3 1751.84
  5497.3 1757.56  5506.6 1758.74  5527.8 1759.74  5538.9 1761.63  5561.5 1767.39
#Mann= 6 ,-1 , 0
  4550.9     .07       0  4680.7      .1       0  4744.9     .07       0
  4981.6     .05       0  4987.7     .07       0  5318.3      .1       0
Bank Sta=4981.6,4987.7
XS Rating Curve= 0 ,0
Exp/Cntr=0.3,0.1