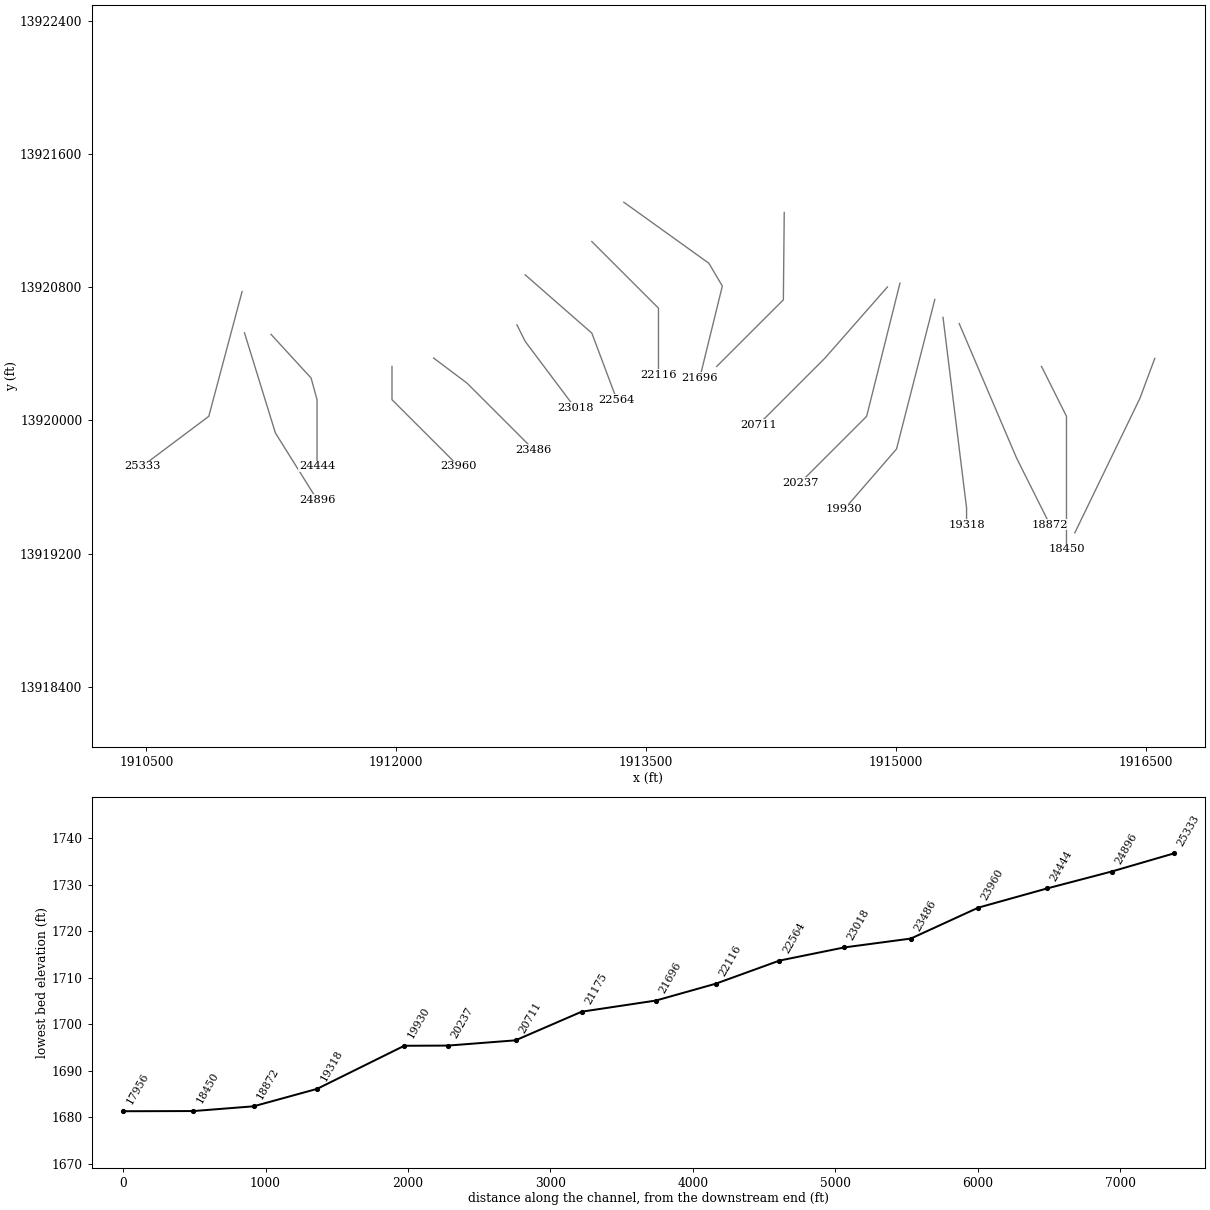
HEC-RAS study Camp Meeting Creek.prj: Camp Meeting Creek Base Level Engineering

--- Camp Meeting Creek.g01 (geometry) --- (continued)

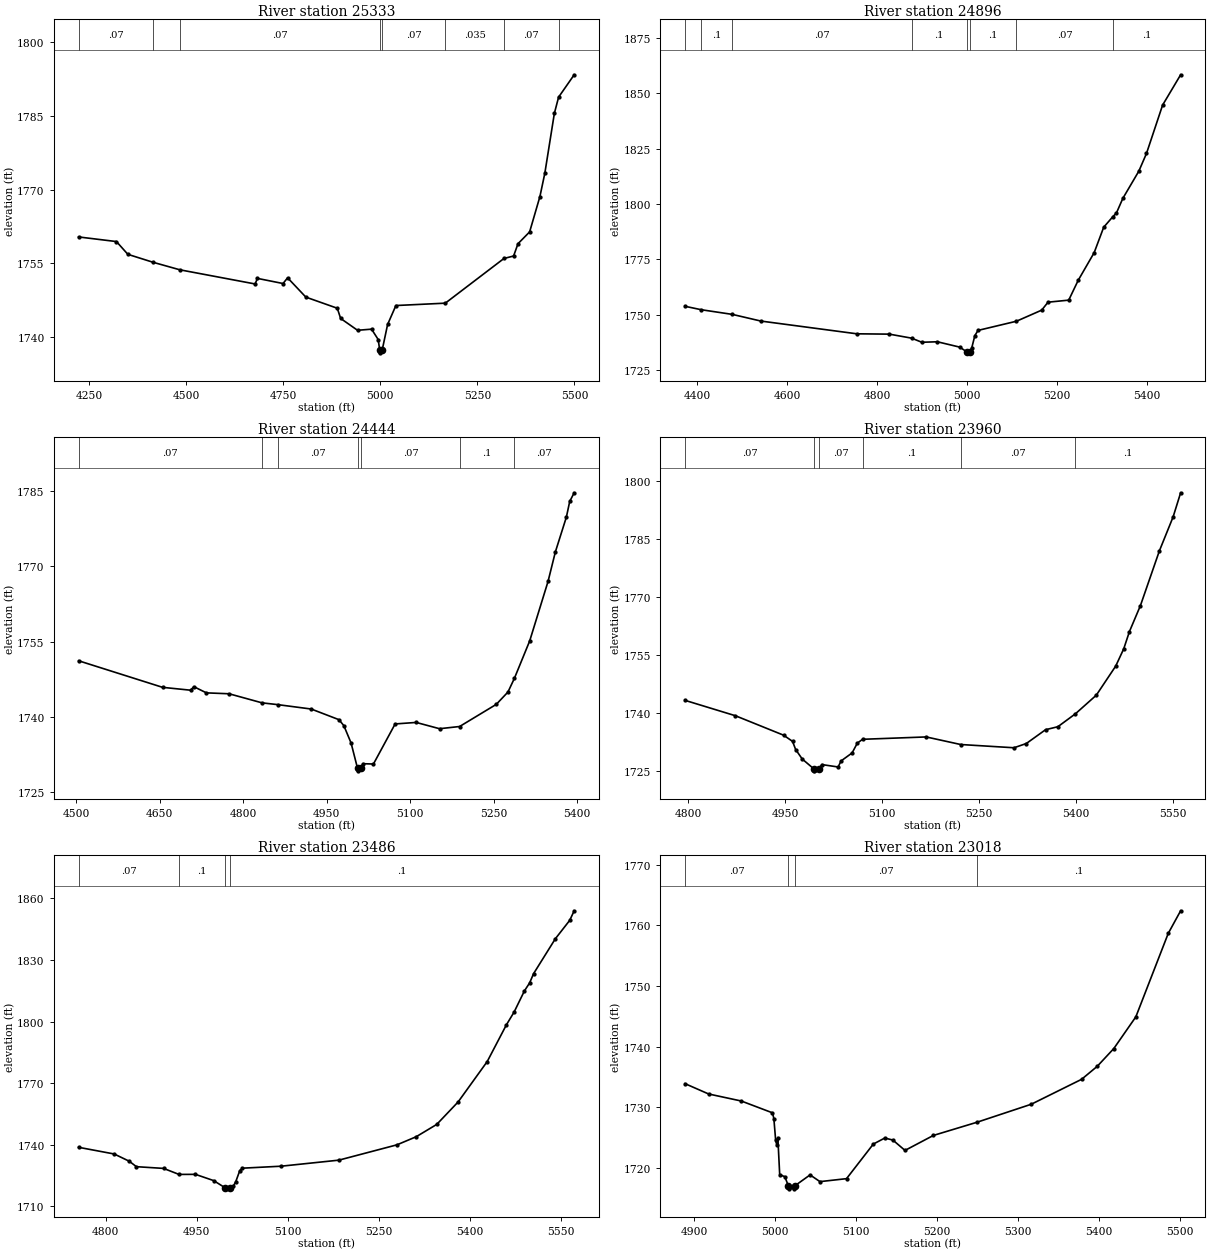
Type RM Length L Ch R = 1 ,25333   ,437,437,437
BEGIN DESCRIPTION:
Camping Meeting Creek 49.0
END DESCRIPTION:
XS GIS Cut Line= 3
        1911075.     13920775.01        1910875.       13920025.
      1910475.02     13919725.01
#Sta/Elev= 30
  4223.2 1760.37  4320.6 1759.43    4350 1756.83    4415 1755.21    4484 1753.68
  4677.6  1750.8  4683.8 1751.93  4749.6 1750.89  4761.4 1752.05  4808.4 1748.12
  4889.3 1745.86    4898 1743.78  4941.5 1741.37  4977.6  1741.6  4994.7 1739.49
  4998.7 1737.28  4999.2 1736.78  5004.8 1737.28  5018.9 1742.55  5040.3 1746.41
  5167.5 1746.89  5318.6 1755.99  5343.4 1756.49  5354.7 1758.99  5384.7  1761.4
  5411.2  1768.6  5423.9 1773.37  5448.4 1785.53  5459.3 1788.83  5499.4 1793.38
#Mann= 8 ,-1 , 0
  4223.2     .07       0    4415      .1       0    4484     .07       0
  4998.7     .05       0  5004.8     .07       0  5167.5    .035       0
  5318.6     .07       0  5459.3    .035       0
Bank Sta=4998.7,5004.8
XS Rating Curve= 0 ,0
Exp/Cntr=0.3,0.1

Type RM Length L Ch R = 1 ,24896   ,452,452,452
BEGIN DESCRIPTION:
Camping Meeting Creek 48.0
END DESCRIPTION:
XS GIS Cut Line= 3
       1911089.3     13920526.87        1911275.       13919925.
      1911525.02     13919524.98
#Sta/Elev= 30
  4373.4 1753.86  4409.6 1752.31  4478.3 1750.22  4541.8 1747.21  4755.3 1741.46
  4827.5 1741.31  4876.7 1739.51  4899.7 1737.65  4934.2 1737.87    4984 1735.45
  4999.2 1733.38  4999.7 1732.88  5005.9 1733.38  5010.4 1734.92  5017.5 1740.62
  5024.5 1742.99    5110 1747.13  5166.1 1752.13  5180.2 1755.72  5226.2 1756.64
  5247.4 1765.63  5282.8 1778.06    5304 1789.53  5323.9 1794.18  5332.3 1795.95
  5346.5 1802.52  5382.1 1814.81  5399.1 1822.79  5434.9 1844.58    5475 1858.25
#Mann= 8 ,-1 , 0
  4373.4     .07       0  4409.6      .1       0  4478.3     .07       0
  4876.7      .1       0  4999.2     .05       0  5005.9      .1       0
    5110     .07       0  5323.9      .1       0
Bank Sta=4999.2,5005.9
XS Rating Curve= 0 ,0
Exp/Cntr=0.3,0.1

Type RM Length L Ch R = 1 ,24444   ,484,484,484
BEGIN DESCRIPTION:
Camping Meeting Creek 47.0
END DESCRIPTION:
XS GIS Cut Line= 4
      1911248.85     13920517.28      1911489.42     13920254.92
        1911525.       13920125.        1911525.     13919724.96
#Sta/Elev= 30
  4504.3 1751.17  4655.2 1745.88  4705.5 1745.31  4711.4 1746.01    4734 1744.78
  4774.7  1744.6    4834 1742.79  4861.9 1742.44  4922.4 1741.56  4972.2 1739.44
    4981 1738.25    4994  1734.8  5005.6 1729.75  5006.1 1729.25  5012.3 1729.75
    5015 1730.67  5034.2 1730.61  5073.2 1738.59    5111 1738.89    5153 1737.64
  5189.1 1738.08    5255 1742.49    5276 1744.95  5287.5 1747.66    5315 1755.11
    5348 1766.96  5361.2 1772.85    5381 1779.79    5387 1782.91    5395 1784.63
#Mann= 7 ,-1 , 0
  4504.3     .07       0    4834      .1       0  4861.9     .07       0
  5005.6     .05       0  5012.3     .07       0  5189.1      .1       0
  5287.5     .07       0
Bank Sta=5005.6,5012.3
XS Rating Curve= 0 ,0
Exp/Cntr=0.3,0.1

Type RM Length L Ch R = 1 ,23960   ,474,474,474
BEGIN DESCRIPTION:
Camping Meeting Creek 46.0
END DESCRIPTION:
XS GIS Cut Line= 3
        1911975.     13920324.96        1911975.       13920125.
      1912374.97     13919725.03
#Sta/Elev= 30
  4795.7 1743.34  4873.5 1739.36  4947.9 1734.33  4961.7 1732.73  4966.5 1730.63
  4976.7 1728.16  4994.7 1725.61  4995.2 1725.11  5002.4 1725.61    5007 1726.73
  5032.1 1726.11  5036.7 1727.67  5053.7 1729.74  5061.8 1732.28  5069.9 1733.27
  5168.2 1733.88  5221.5 1731.92  5303.8 1731.08  5322.9 1732.18  5352.6 1735.75
  5371.6 1736.52  5398.7 1739.86    5431 1744.68    5461 1752.21  5473.4 1756.68
  5482.2 1761.14  5499.2 1767.87  5528.5 1782.03  5549.7 1790.81  5561.3 1797.04
#Mann= 6 ,-1 , 0
  4795.7     .07       0  4994.7     .05       0  5002.4     .07       0
  5069.9      .1       0  5221.5     .07       0  5398.7      .1       0
Bank Sta=4994.7,5002.4
XS Rating Curve= 0 ,0
Exp/Cntr=0.3,0.1

Type RM Length L Ch R = 1 ,23486   ,468,468,468
BEGIN DESCRIPTION:
Camping Meeting Creek 45.0
END DESCRIPTION:
XS GIS Cut Line= 3
      1912224.96     13920375.03        1912425.       13920225.
      1912824.98     13919825.02
#Sta/Elev= 30
  4755.4 1738.69  4813.9 1735.44  4838.9 1731.88  4850.5 1729.25  4895.2 1728.41
  4920.6 1725.48  4947.7 1725.51  4977.7 1722.46  4996.6 1718.95  4997.1 1718.45
  5004.4 1718.95  5009.7 1719.62    5014 1721.89  5020.7 1727.36    5025 1728.52
  5088.6 1729.48  5183.7 1732.43  5279.5 1739.91    5311 1743.84  5344.9 1749.86
  5380.1 1760.82    5428 1780.51  5459.5 1798.37  5472.2 1804.61  5489.2 1814.93
  5497.7 1818.78  5504.4  1823.4  5540.1 1840.34  5563.8 1849.33  5571.1 1853.98
#Mann= 4 ,-1 , 0
  4755.4     .07       0  4920.6      .1       0  4996.6     .05       0
  5004.4      .1       0
Bank Sta=4996.6,5004.4
XS Rating Curve= 0 ,0
Exp/Cntr=0.3,0.1

Type RM Length L Ch R = 1 ,23018   ,454,454,454
BEGIN DESCRIPTION:
Camping Meeting Creek 44.0
END DESCRIPTION:
XS GIS Cut Line= 3
      1912725.01     13920574.99        1912775.       13920475.
      1913075.01     13920074.99
#Sta/Elev= 30
  4889.1 1733.89  4918.2 1732.19  4958.5 1731.03    4997 1729.08  4998.7 1728.12
  5000.9 1724.56  5002.2 1723.83  5003.6    1725  5005.9 1718.87  5012.2 1718.55
  5016.6 1717.04  5017.1 1716.54  5024.1 1716.54  5024.6 1717.04  5043.4 1718.84
  5055.6 1717.73  5088.4 1718.22  5121.5 1723.93  5135.6 1724.92  5145.6 1724.59
  5160.6 1722.88  5195.6 1725.35  5249.3 1727.52  5316.5  1730.5  5378.6 1734.61
  5397.9 1736.75  5418.4 1739.69  5445.6 1744.92  5485.6 1758.69  5500.9 1762.42
#Mann= 4 ,-1 , 0
  4889.1     .07       0  5016.6     .05       0  5024.6     .07       0
  5249.3      .1       0
Bank Sta=5016.6,5024.6
XS Rating Curve= 0 ,0
Exp/Cntr=0.3,0.1

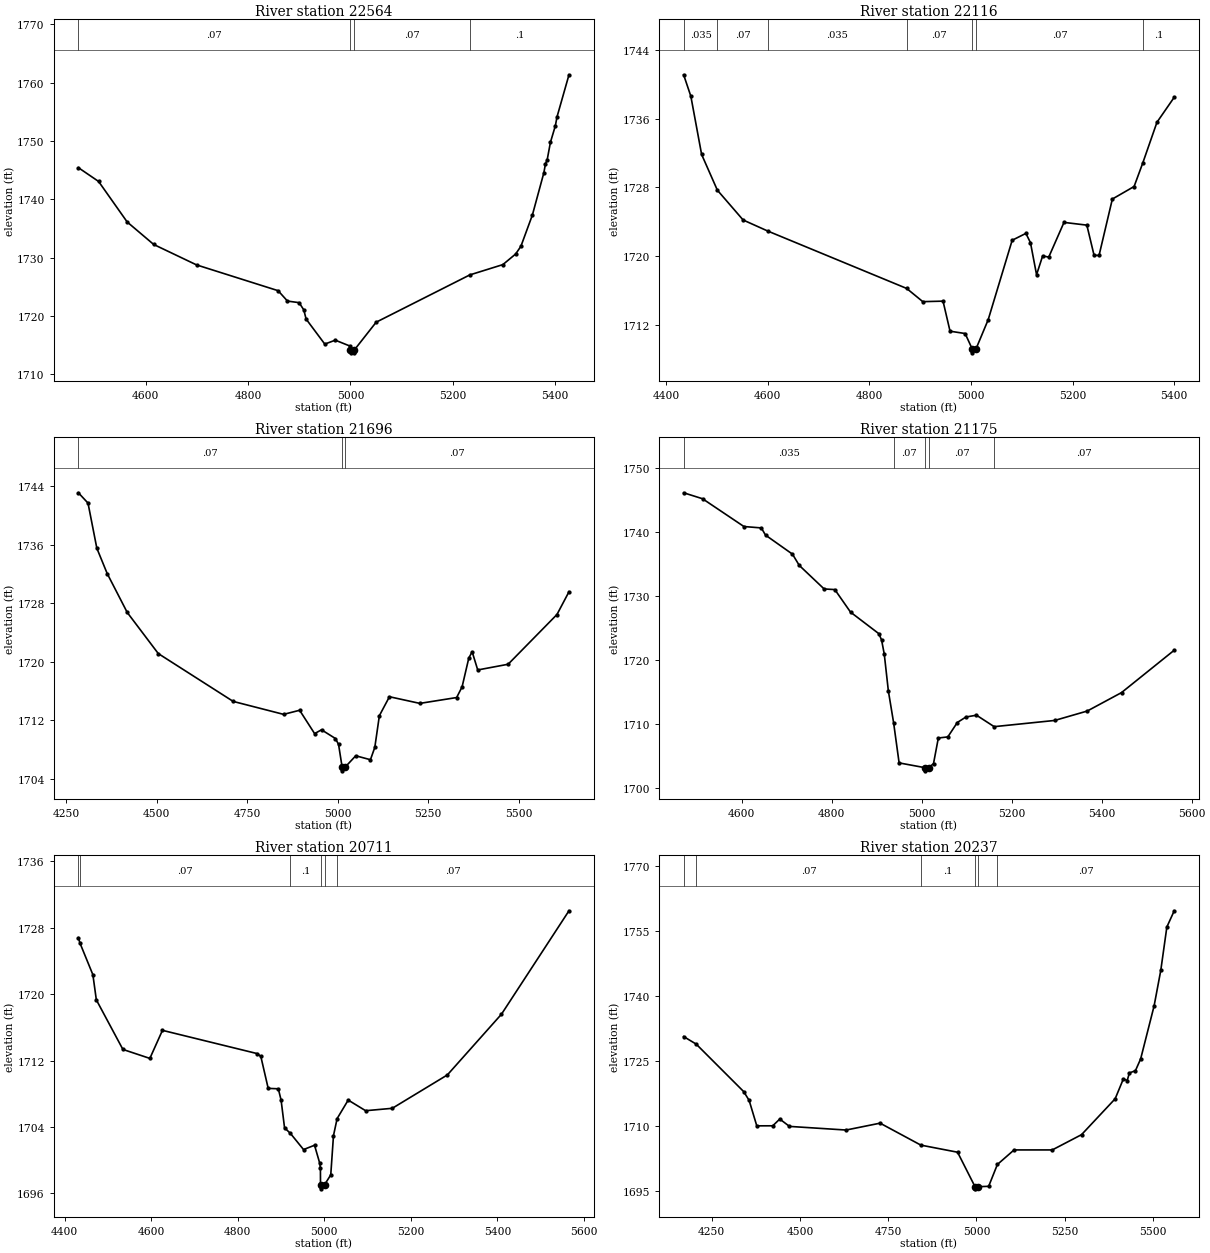
Type RM Length L Ch R = 1 ,22564   ,448,448,448
BEGIN DESCRIPTION:
Camping Meeting Creek 43.0
END DESCRIPTION:
XS GIS Cut Line= 3
        1912775.       13920875.        1913175.       13920525.
        1913325.     13920125.01
#Sta/Elev= 30
  4468.4 1745.44  4507.9 1743.08  4563.8 1736.13  4615.6 1732.28  4699.3 1728.78
  4858.7 1724.36    4877 1722.58  4899.7 1722.31  4908.9 1721.07  4913.4  1719.5
  4949.9 1715.21  4970.4 1715.88  4998.3  1714.9  4999.7 1714.21  5000.2 1713.71
  5007.2 1713.71  5007.7 1714.21  5050.3 1718.96  5233.2 1727.06  5297.9 1728.83
  5322.9 1730.65  5333.2 1731.98  5355.6 1737.33    5378 1744.57  5381.2 1746.12
  5384.4 1746.74  5390.8 1749.77  5400.5 1752.63  5403.7 1754.14  5427.1 1761.36
#Mann= 4 ,-1 , 0
  4468.4     .07       0  4999.7     .05       0  5007.7     .07       0
  5233.2      .1       0
Bank Sta=4999.7,5007.7
XS Rating Curve= 0 ,0
Exp/Cntr=0.3,0.1

Type RM Length L Ch R = 1 ,22116   ,420,420,420
BEGIN DESCRIPTION:
Camping Meeting Creek 42.0
END DESCRIPTION:
XS GIS Cut Line= 3
      1913174.99     13921075.01        1913575.       13920675.
        1913575.       13920275.
#Sta/Elev= 30
  4434.3 1741.11  4448.5 1738.61  4469.7 1731.83  4500.7 1727.67  4551.4  1724.2
    4600 1722.91  4873.3 1716.23  4905.1 1714.69  4944.9 1714.75  4958.7 1711.25
  4988.4 1710.98    5002 1709.23  5002.5 1708.73  5010.1 1709.23  5033.8 1712.59
    5081 1721.84    5108 1722.64    5117 1721.56    5129 1717.83    5141 1720.02
    5153 1719.88    5183 1723.92    5228  1723.6  5242.2 1720.09    5252 1720.07
  5278.2 1726.64    5321  1728.1  5338.2 1730.86    5366 1735.58    5400 1738.49
#Mann= 7 ,-1 , 0
  4434.3    .035       0  4500.7     .07       0    4600    .035       0
  4873.3     .07       0    5002     .05       0  5010.1     .07       0
  5338.2      .1       0
Bank Sta=5002,5010.1
XS Rating Curve= 0 ,0
Exp/Cntr=0.3,0.1

Type RM Length L Ch R = 1 ,21696   ,521,521,521
BEGIN DESCRIPTION:
Camping Meeting Creek 41.0
END DESCRIPTION:
XS GIS Cut Line= 4
      1913367.16     13921311.45      1913877.84     13920944.76
      1913958.53     13920807.83      1913823.18     13920256.02
#Sta/Elev= 30
  4283.4 1743.12    4310 1741.71  4334.4 1735.54    4363 1732.08  4418.4 1726.76
  4504.2 1721.14  4711.2  1714.6  4850.5 1712.83  4894.8 1713.39  4936.2  1710.2
  4955.3 1710.72  4993.7 1709.53  5002.4 1708.72  5012.3 1705.61  5012.8 1705.11
  5020.4 1705.61  5049.9 1707.17  5090.5 1706.63  5102.6 1708.32  5115.2 1712.65
    5143 1715.24    5227 1714.33  5328.7 1715.13  5343.8 1716.59  5362.3 1720.52
  5371.6 1721.39    5387  1718.9    5471 1719.68    5606 1726.48  5639.2 1729.59
#Mann= 3 ,-1 , 0
  4283.4     .07       0  5012.3     .05       0  5020.4     .07       0
Bank Sta=5012.3,5020.4
XS Rating Curve= 0 ,0
Exp/Cntr=0.3,0.1

Type RM Length L Ch R = 1 ,21175   ,464,464,464
BEGIN DESCRIPTION:
Camping Meeting Creek 40.0
END DESCRIPTION:
XS GIS Cut Line= 3
      1914330.28     13921249.91        1914325.       13920725.
      1913925.01     13920325.01
#Sta/Elev= 30
  4470.7 1746.14  4512.7 1745.21  4604.7 1740.87  4643.4 1740.65  4652.7 1739.53
  4712.7 1736.55  4727.7  1734.8    4783 1731.12  4806.8 1731.02  4841.7  1727.5
  4904.7 1724.13  4910.7 1723.15  4916.7 1720.95  4925.8 1715.19  4937.4 1710.26
  4949.7 1703.95  5006.6 1703.21  5007.1 1702.71  5015.9 1703.21  5026.2 1703.85
  5036.9 1707.84    5058 1708.01  5079.1 1710.26  5098.3 1711.12  5121.7  1711.4
    5161 1709.61  5295.5 1710.58  5367.9 1712.05  5444.1 1714.93  5561.3 1721.55
#Mann= 5 ,-1 , 0
  4470.7    .035       0  4937.4     .07       0  5006.6     .05       0
  5015.9     .07       0    5161     .07       0
Bank Sta=5006.6,5015.9
XS Rating Curve= 0 ,0
Exp/Cntr=0.3,0.1

Type RM Length L Ch R = 1 ,20711   ,474,474,474
BEGIN DESCRIPTION:
Camping Meeting Creek 39.0
END DESCRIPTION:
XS GIS Cut Line= 3
      1914949.76     13920802.15        1914575.       13920375.
      1914175.02     13919975.02
#Sta/Elev= 30
  4431.5  1726.8  4434.9 1726.18    4465 1722.34    4473 1719.31  4534.4 1713.34
  4596.7 1712.26  4625.8 1715.64  4844.7 1712.84  4853.2 1712.49  4870.2 1708.65
  4893.6  1708.6    4900 1707.24    4908  1703.9  4921.5 1703.23  4951.9 1701.28
  4977.3  1701.8  4989.3 1699.64  4990.9 1699.02  4991.1 1697.05  4991.6 1696.55
  5000.5 1697.05  5014.8 1698.23  5021.1 1702.96  5029.5 1705.01  5055.1 1707.24
  5095.4 1705.96    5157 1706.25  5284.3 1710.27  5409.3 1717.58  5565.4 1730.04
#Mann= 6 ,-1 , 0
  4431.5      .1       0  4434.9     .07       0  4921.5      .1       0
  4991.1     .05       0  5000.5      .1       0  5029.5     .07       0
Bank Sta=4991.1,5000.5
XS Rating Curve= 0 ,0
Exp/Cntr=0.3,0.1

Type RM Length L Ch R = 1 ,20237   ,307,307,307
BEGIN DESCRIPTION:
Camping Meeting Creek 38.0
END DESCRIPTION:
XS GIS Cut Line= 3
      1915025.01     13920825.03        1914825.       13920025.
      1914425.03     13919625.03
#Sta/Elev= 30
  4170.3 1730.64  4205.9 1728.89  4340.5 1717.91  4355.9 1715.88  4377.6 1709.99
  4422.9    1710  4442.7 1711.56  4470.3 1709.86  4630.7 1709.02    4727 1710.61
  4842.6 1705.53  4946.6 1703.89    4996 1695.92  4996.5 1695.42  5005.5 1695.92
  5034.7    1696  5059.4 1701.05  5106.7 1704.42    5215 1704.42  5297.9 1707.95
  5393.2 1716.25  5416.6 1720.88  5427.2 1720.45  5433.6 1722.23  5450.6 1722.74
  5465.4 1725.46  5503.5 1737.71  5522.5 1745.96  5539.7 1755.98  5560.6 1759.73
#Mann= 6 ,-1 , 0
  4170.3      .1       0  4205.9     .07       0  4842.6      .1       0
    4996     .05       0  5005.5      .1       0  5059.4     .07       0
Bank Sta=4996,5005.5
XS Rating Curve= 0 ,0
Exp/Cntr=0.3,0.1

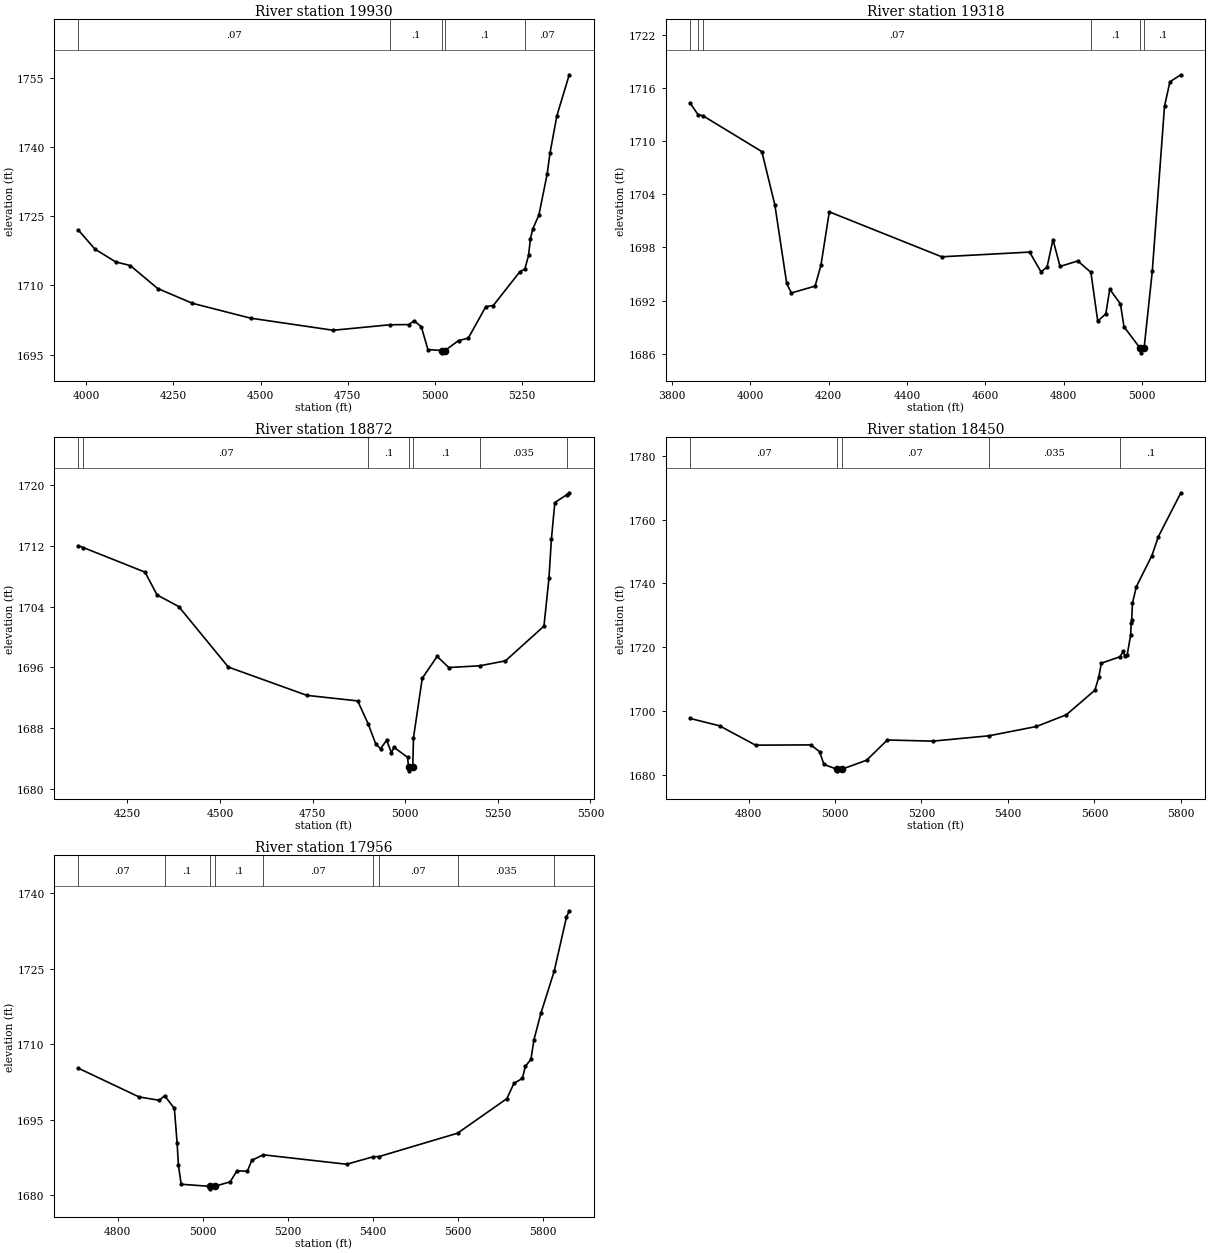
Type RM Length L Ch R = 1 ,19930   ,612,612,612
BEGIN DESCRIPTION:
Camping Meeting Creek 37.1
END DESCRIPTION:
XS GIS Cut Line= 3
      1915234.47     13920727.27      1915004.32     13919828.38
      1914690.53     13919466.19
#Sta/Elev= 30
  3977.9 1721.96  4025.7 1717.83  4084.7 1715.08  4126.6 1714.29  4205.3 1709.31
  4304.9 1706.11  4471.6 1702.89  4708.5 1700.27  4870.9 1701.46  4924.9  1701.5
  4940.7 1702.32    4961 1701.02  4979.9 1696.09  5019.3 1695.88  5019.8 1695.38
  5028.8 1695.88  5067.8 1698.04  5095.5 1698.55  5146.1 1705.41  5167.3 1705.63
  5243.9 1712.99  5257.7  1713.5  5268.5 1716.51  5273.7 1720.06  5280.1 1722.13
    5298 1725.23  5321.8 1734.14  5329.7 1738.57  5349.6 1746.74    5385 1755.61
#Mann= 5 ,-1 , 0
  3977.9     .07       0  4870.9      .1       0  5019.3     .05       0
  5028.8      .1       0  5257.7     .07       0
Bank Sta=5019.3,5028.8
XS Rating Curve= 0 ,0
Exp/Cntr=0.3,0.1

Type RM Length L Ch R = 1 ,19318   ,446,446,446
BEGIN DESCRIPTION:
Camping Meeting Creek 37.0
END DESCRIPTION:
XS GIS Cut Line= 3
      1915283.54     13920619.95        1915425.       13919475.
        1915425.     13919374.96
#Sta/Elev= 30
  3845.9 1714.29  3866.5 1712.97  3878.4 1712.87  4029.3 1708.81  4062.5  1702.8
  4092.8 1693.93  4104.8 1692.86  4165.3 1693.63  4180.4 1696.02  4201.6 1702.01
  4488.7 1696.94  4713.3 1697.47  4742.3 1695.24  4757.8 1695.77  4772.9 1698.88
    4791 1695.85  4836.4 1696.47  4869.8 1695.18  4887.2 1689.69  4907.9  1690.5
    4918 1693.28  4945.2 1691.62  4954.3 1689.04    4996  1686.6  4996.5  1686.1
  5005.6  1686.6  5026.6 1695.32  5057.8 1713.92  5071.6 1716.69  5099.6 1717.48
#Mann= 6 ,-1 , 0
  3845.9     .07       0  3866.5    .035       0  3878.4     .07       0
  4869.8      .1       0    4996     .05       0  5005.6      .1       0
Bank Sta=4996,5005.6
XS Rating Curve= 0 ,0
Exp/Cntr=0.3,0.1

Type RM Length L Ch R = 1 ,18872   ,422,422,422
BEGIN DESCRIPTION:
Camping Meeting Creek 36.0
END DESCRIPTION:
XS GIS Cut Line= 3
      1915380.81     13920582.34        1915725.       13919775.
      1915925.02     13919374.97
#Sta/Elev= 30
    4118 1712.03  4131.1 1711.79  4297.8 1708.55  4330.4 1705.54  4388.8 1704.01
  4522.8 1696.03  4734.8  1692.3  4871.8 1691.57  4899.9 1688.58  4920.7 1685.88
  4933.7 1685.27    4950 1686.38  4963.1 1684.72  4969.6 1685.46  5006.4 1684.14
  5009.3 1682.85  5009.8 1682.35  5020.5 1682.85  5022.5 1686.71  5046.2 1694.55
  5086.3 1697.44  5117.8 1695.97  5201.4  1696.2  5270.7 1696.85  5374.7 1701.43
  5388.1 1707.71  5394.8 1712.88    5404 1717.72  5436.7 1718.77  5442.9 1719.01
#Mann= 7 ,-1 , 0
    4118    .035       0  4131.1     .07       0  4899.9      .1       0
  5009.3     .05       0  5020.5      .1       0  5201.4    .035       0
  5436.7      .1       0
Bank Sta=5009.3,5020.5
XS Rating Curve= 0 ,0
Exp/Cntr=0.3,0.1

Type RM Length L Ch R = 1 ,18450   ,494,494,494
BEGIN DESCRIPTION:
Camping Meeting Creek 35.0
END DESCRIPTION:
XS GIS Cut Line= 3
      1915875.01     13920324.98        1916025.       13920025.
        1916025.     13919224.99
#Sta/Elev= 30
  4664.6 1697.74  4732.8 1695.43  4816.2 1689.37  4944.1 1689.45  4964.3 1687.31
  4974.3 1683.34  5004.4 1681.83  5004.9 1681.33  5015.6 1681.83    5073 1684.65
    5121 1690.99    5226 1690.63    5356  1692.3    5466 1695.22    5535 1698.88
    5601 1706.56    5610 1710.58    5616 1715.02  5658.9 1717.04    5667 1718.77
    5670 1717.29    5676 1717.75  5683.8 1723.82    5685 1727.56  5686.2 1728.57
    5688 1733.79    5697    1739    5733 1748.72    5748 1754.67    5800 1768.38
#Mann= 5 ,-1 , 0
  4664.6     .07       0  5004.4     .05       0  5015.6     .07       0
    5356    .035       0  5658.9      .1       0
Bank Sta=5004.4,5015.6
XS Rating Curve= 0 ,0
Exp/Cntr=0.3,0.1

Type RM Length L Ch R = 1 ,17956   ,438,438,438
BEGIN DESCRIPTION:
Camping Meeting Creek 34.0
END DESCRIPTION:
XS GIS Cut Line= 3
      1916555.18     13920373.54      1916466.19      13920133.8
      1916074.98     13919324.97
#Sta/Elev= 30
    4708 1705.22  4850.5 1699.53  4898.5 1698.85  4910.7 1699.76  4933.7 1697.25
  4940.1 1690.39  4943.3 1685.93  4949.7  1682.2  5016.6 1681.79  5017.1 1681.29
  5028.3 1681.79    5065 1682.68  5080.7 1684.85  5105.4  1684.8  5115.7 1686.94
  5142.6 1688.04    5339 1686.17  5401.3 1687.66  5414.8 1687.69  5599.6 1692.33
  5715.6 1699.19  5732.2 1702.23  5752.2 1703.21  5758.9 1705.59  5772.2 1706.99
  5779.2 1710.85  5795.6 1716.13  5826.8 1724.46  5855.7 1735.19  5862.2 1736.46
#Mann= 9 ,-1 , 0
    4708     .07       0  4910.7      .1       0  5016.6     .05       0
  5028.3      .1       0  5142.6     .07       0  5401.3      .1       0
  5414.8     .07       0  5599.6    .035       0  5826.8      .1       0
Bank Sta=5016.6,5028.3
XS Rating Curve= 0 ,0
Exp/Cntr=0.3,0.1