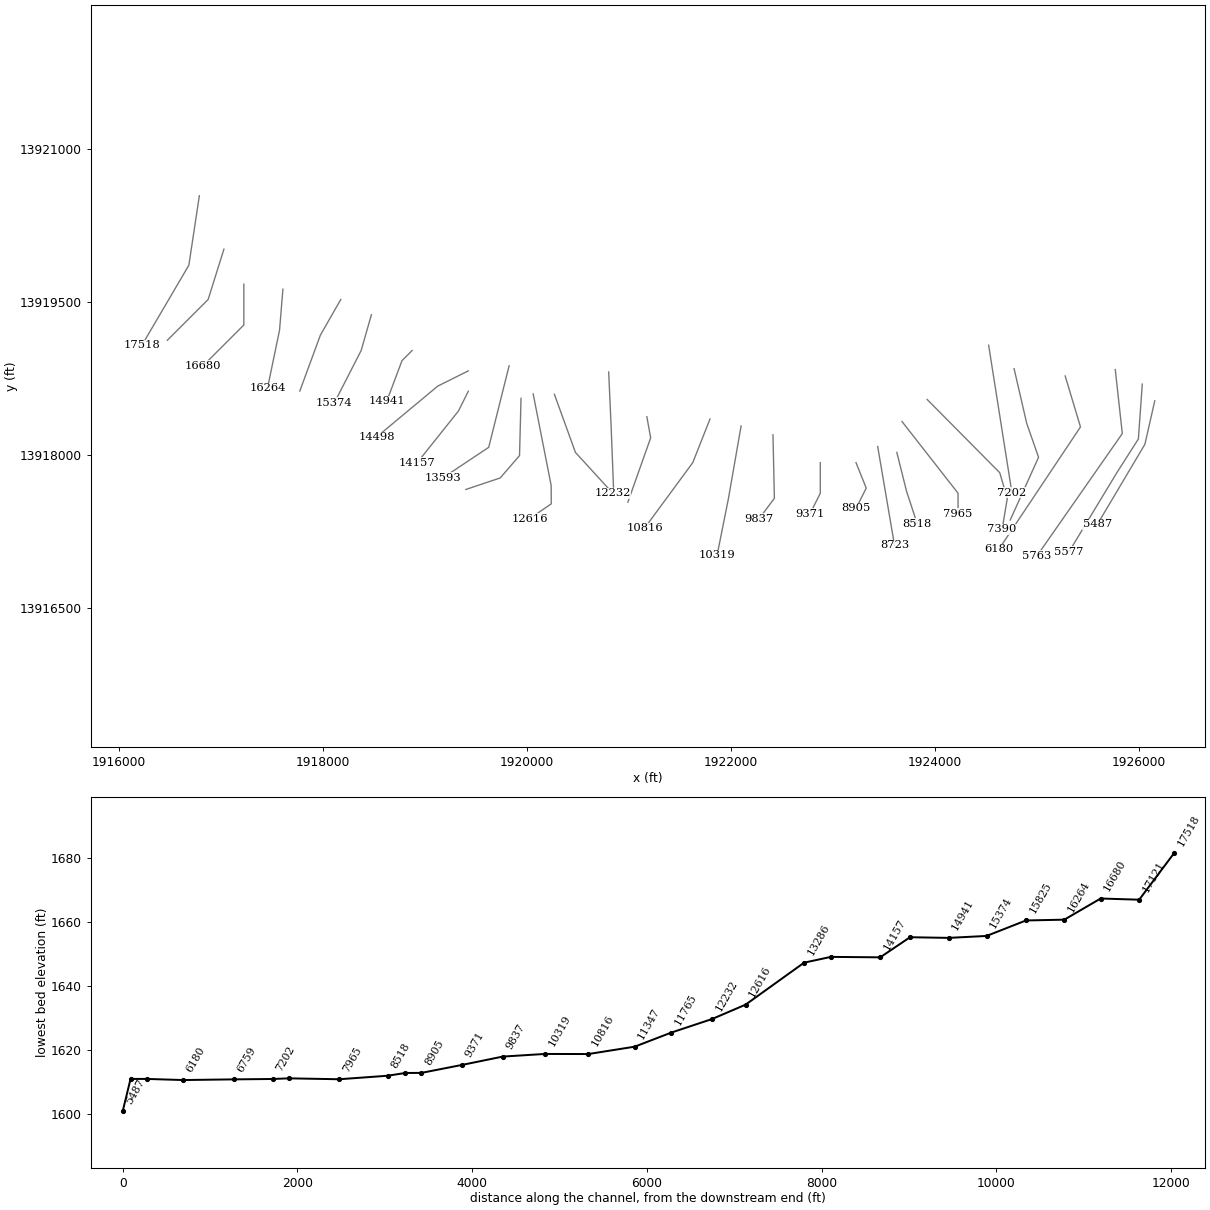
HEC-RAS study Camp Meeting Creek.prj: Camp Meeting Creek Base Level Engineering

--- Camp Meeting Creek.g01 (geometry) --- (continued)

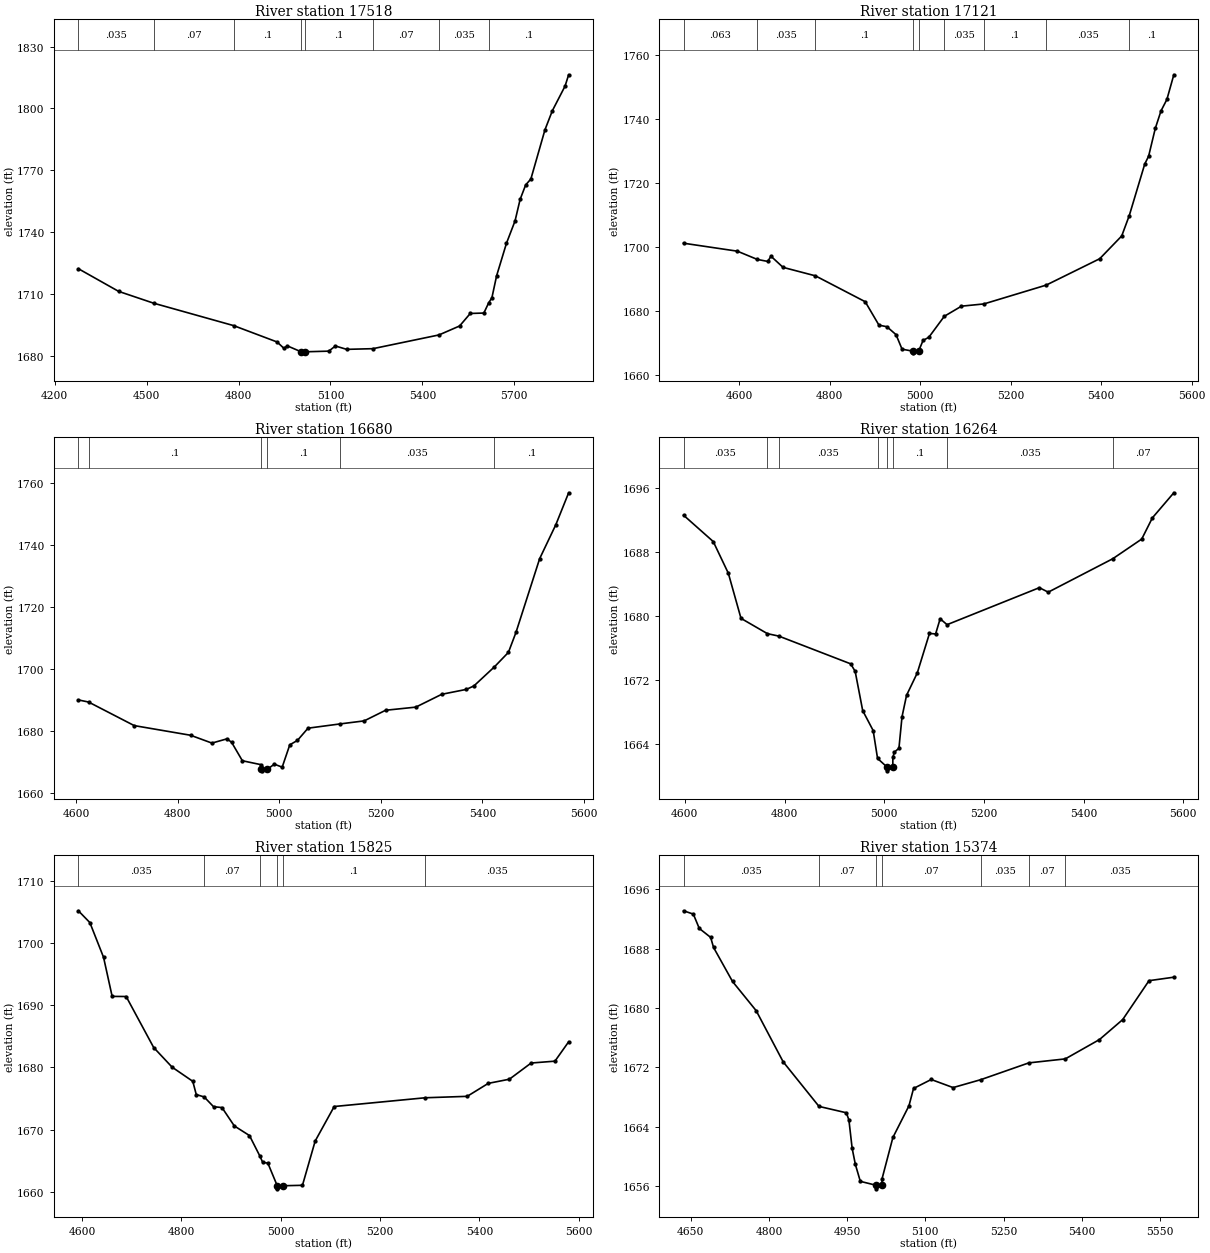
Type RM Length L Ch R = 1 ,17518   ,397,397,397
BEGIN DESCRIPTION:
Camping Meeting Creek 33.0
END DESCRIPTION:
XS GIS Cut Line= 3
      1916788.91     13920542.43        1916686.     13919860.93
      1916224.99     13919074.98
#Sta/Elev= 30
  4277.1 1722.19  4408.5 1711.19  4522.7 1705.46  4784.2 1694.56  4925.8 1686.63
  4948.2 1683.53  4959.2 1684.74  5004.4 1681.86  5004.9 1681.36  5016.2 1681.86
  5094.3 1682.18  5116.2 1684.68  5152.9 1683.05  5238.6 1683.38  5454.3 1690.05
  5521.6  1694.4  5556.4 1700.47  5600.7 1700.67  5616.4 1705.59    5627 1708.09
  5642.4 1718.78  5674.6 1734.56  5702.5 1745.37  5719.1 1755.83  5737.2 1762.85
  5754.2 1765.72  5800.2 1789.61  5824.2 1798.82  5865.9 1810.84  5877.5  1816.3
#Mann= 8 ,-1 , 0
  4277.1    .035       0  4522.7     .07       0  4784.2      .1       0
  5004.4     .05       0  5016.2      .1       0  5238.6     .07       0
  5454.3    .035       0  5616.4      .1       0
Bank Sta=5004.4,5016.2
XS Rating Curve= 0 ,0
Exp/Cntr=0.3,0.1

Type RM Length L Ch R = 1 ,17121   ,441,441,441
BEGIN DESCRIPTION:
Camping Meeting Creek 32.0
END DESCRIPTION:
XS GIS Cut Line= 3
      1917029.88     13920019.08        1916875.       13919525.
      1916474.98     13919124.98
#Sta/Elev= 30
  4477.1 1701.15  4596.1 1698.66    4640 1696.09  4663.2 1695.46  4670.3 1697.09
    4697 1693.61  4768.6 1690.96  4878.6 1682.88    4909 1675.56  4926.5 1675.08
  4946.7  1672.6    4960 1668.06  4984.8 1667.42  4985.3 1666.92  4996.6 1667.42
  5006.4 1670.79  5019.2 1671.78  5053.4 1678.33  5091.3 1681.49  5140.9 1682.19
  5278.6 1688.07  5396.8  1696.3  5445.5 1703.42  5462.2  1709.8  5496.4 1725.89
  5504.9 1728.32  5519.6 1736.97  5532.3 1742.47  5545.3 1746.04  5560.6 1753.74
#Mann= 9 ,-1 , 0
  4477.1    .063       0    4640    .035       0  4768.6      .1       0
  4984.8     .05       0  4996.6      .1       0  5053.4    .035       0
  5140.9      .1       0  5278.6    .035       0  5462.2      .1       0
Bank Sta=4984.8,4996.6
XS Rating Curve= 0 ,0
Exp/Cntr=0.3,0.1

Type RM Length L Ch R = 1 ,16680   ,416,416,416
BEGIN DESCRIPTION:
Camping Meeting Creek 31.0
END DESCRIPTION:
XS GIS Cut Line= 3
        1917225.     13919674.95        1917225.       13919275.
      1916825.03     13918875.03
#Sta/Elev= 30
  4604.4 1690.13  4624.5 1689.45  4714.4 1681.86  4825.4 1678.75  4867.4 1676.23
  4897.4 1677.61  4906.4 1676.43  4927.4 1670.54  4963.4  1669.3  4964.6 1667.79
  4965.1 1667.29  4976.5 1667.79  4990.4 1669.44  5005.8 1668.47  5020.8 1675.67
  5035.8 1677.08  5056.7 1681.03  5118.8 1682.38  5167.3 1683.38  5209.5  1686.8
    5269 1687.81    5320 1691.94  5368.7 1693.53  5383.5 1694.65  5423.8 1700.78
  5451.4 1705.45  5466.3 1711.89  5512.9 1735.63  5544.9 1746.62    5570 1756.85
#Mann= 6 ,-1 , 0
  4604.4    .035       0  4624.5      .1       0  4964.6     .05       0
  4976.5      .1       0  5118.8    .035       0  5423.8      .1       0
Bank Sta=4964.6,4976.5
XS Rating Curve= 0 ,0
Exp/Cntr=0.3,0.1

Type RM Length L Ch R = 1 ,16264   ,439,439,439
BEGIN DESCRIPTION:
Camping Meeting Creek 30.0
END DESCRIPTION:
XS GIS Cut Line= 3
      1917607.83     13919626.23        1917575.       13919225.
      1917457.06     13918655.86
#Sta/Elev= 30
  4597.4 1692.61    4657 1689.32  4687.3 1685.36  4712.7 1679.73  4765.7 1677.82
  4788.8 1677.51  4932.8 1674.05  4941.8 1673.11  4956.9 1668.21  4977.9 1665.72
  4986.7 1662.24  5005.2 1661.19  5005.7 1660.69  5017.3 1661.19  5017.4 1662.36
  5020.4 1663.03  5029.6  1663.5  5035.8 1667.44  5044.9 1670.12  5066.4 1672.91
  5090.9 1677.85  5103.2 1677.78  5112.3 1679.68  5126.2 1678.94  5311.4 1683.56
  5329.2    1683  5458.6 1687.17  5516.8 1689.63  5538.2 1692.28  5581.2 1695.41
#Mann= 8 ,-1 , 0
  4597.4    .035       0  4765.7     .07       0  4788.8    .035       0
  4986.7      .1       0  5005.2     .05       0  5017.3      .1       0
  5126.2    .035       0  5458.6     .07       0
Bank Sta=5005.2,5017.3
XS Rating Curve= 0 ,0
Exp/Cntr=0.3,0.1

Type RM Length L Ch R = 1 ,15825   ,451,451,451
BEGIN DESCRIPTION:
Camping Meeting Creek 29.0
END DESCRIPTION:
XS GIS Cut Line= 3
      1918175.01     13919525.01        1917975.       13919175.
      1917773.63     13918627.05
#Sta/Elev= 30
  4592.8 1705.26  4615.9 1703.36  4643.5 1697.76  4660.8 1691.46    4689 1691.44
  4744.4 1683.22  4781.4 1680.06  4823.1 1677.77  4830.1 1675.64  4846.1 1675.25
  4864.9 1673.68  4881.9 1673.54  4906.7 1670.58  4937.2 1669.03  4958.3  1665.7
  4963.9  1664.7  4974.2 1664.59  4993.1 1660.94  4993.6 1660.44  5005.3 1660.94
  5043.9 1661.01  5069.5 1668.15  5107.8 1673.71    5291 1675.12  5375.5 1675.35
  5417.9 1677.44  5460.4 1678.11  5504.2 1680.72  5552.1 1681.02  5579.7 1684.14
#Mann= 6 ,-1 , 0
  4592.8    .035       0  4846.1     .07       0  4958.3      .1       0
  4993.1     .05       0  5005.3      .1       0    5291    .035       0
Bank Sta=4993.1,5005.3
XS Rating Curve= 0 ,0
Exp/Cntr=0.3,0.1

Type RM Length L Ch R = 1 ,15374   ,433,433,433
BEGIN DESCRIPTION:
Camping Meeting Creek 28.0
END DESCRIPTION:
XS GIS Cut Line= 3
        1918475.     13919374.99        1918375.       13919025.
      1918112.27     13918511.62
#Sta/Elev= 30
    4636 1693.12  4654.8 1692.67  4666.2 1690.74    4688 1689.53  4693.6 1688.17
    4730 1683.58  4775.4 1679.64  4827.1 1672.75  4895.9 1666.73  4948.4 1665.87
  4953.3  1664.9  4959.5 1661.08  4965.7  1658.9  4975.2 1656.62  5004.4 1656.11
  5004.9 1655.61  5016.7 1656.11  5016.9 1656.97  5037.7 1662.54  5068.5 1666.81
  5077.3 1669.15  5111.2 1670.36  5153.2 1669.27  5206.5 1670.34  5298.4  1672.6
  5368.5 1673.14  5434.1 1675.75  5478.6 1678.44  5529.1 1683.69  5576.7 1684.16
#Mann= 7 ,-1 , 0
    4636    .035       0  4895.9     .07       0  5004.4     .05       0
  5016.7     .07       0  5206.5    .035       0  5298.4     .07       0
  5368.5    .035       0
Bank Sta=5004.4,5016.7
XS Rating Curve= 0 ,0
Exp/Cntr=0.3,0.1

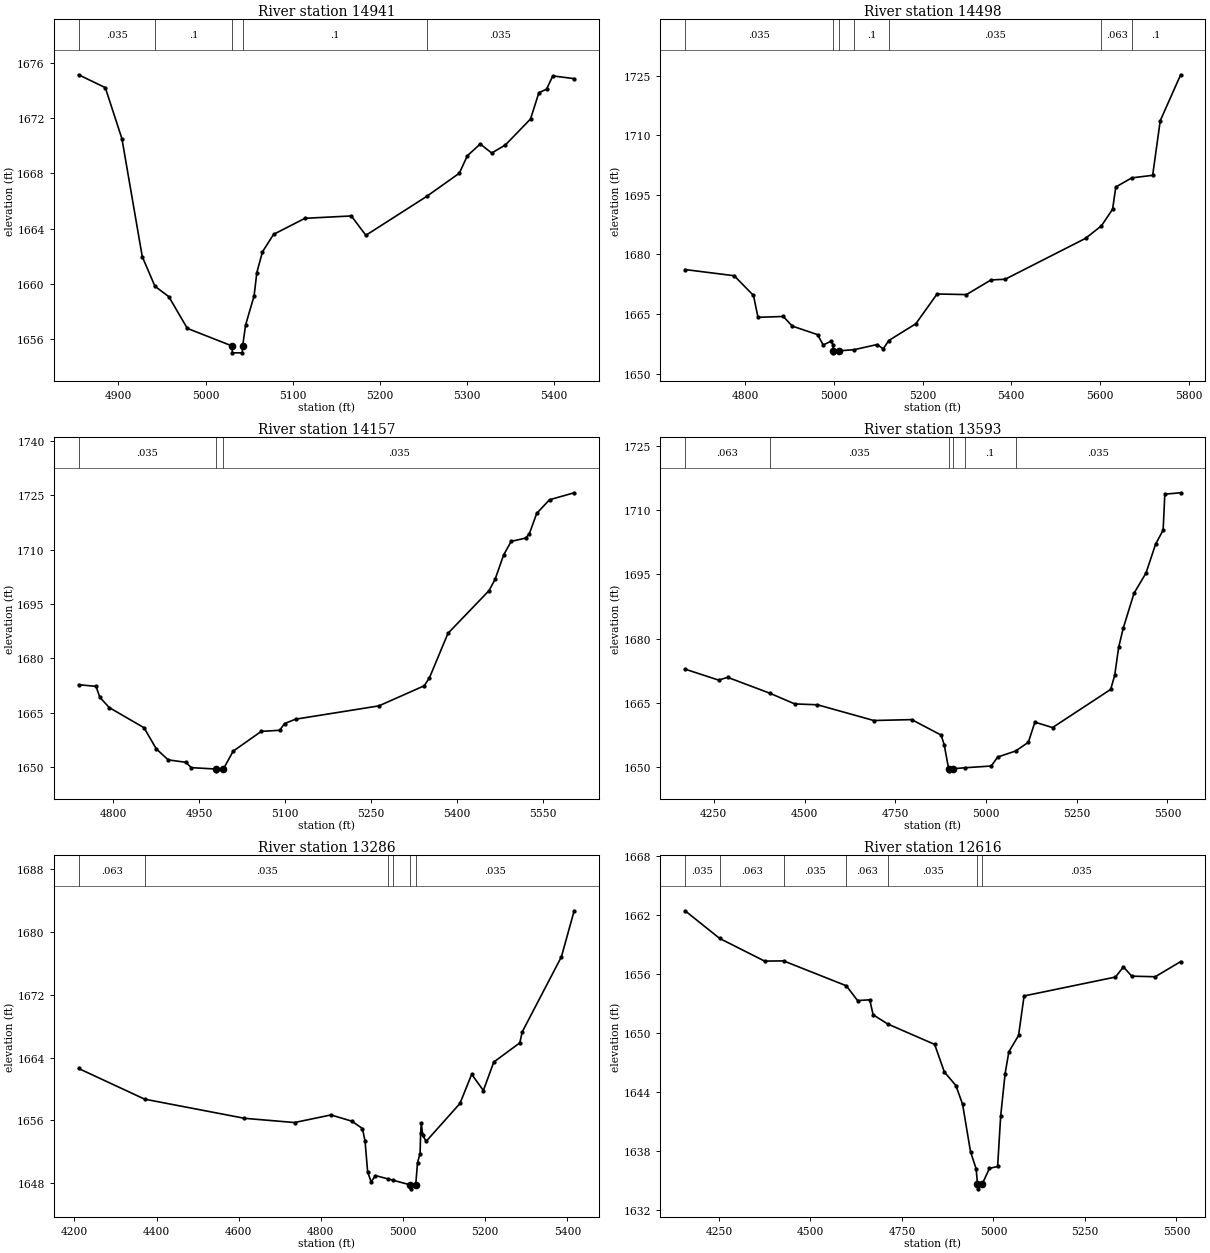
Type RM Length L Ch R = 1 ,14941   ,443,443,443
BEGIN DESCRIPTION:
Camping Meeting Creek 27.0
END DESCRIPTION:
XS GIS Cut Line= 3
      1918874.99     13919024.99        1918775.       13918925.
        1918625.     13918525.01
#Sta/Elev= 30
  4854.3 1675.12  4884.9 1674.19    4904 1670.49  4927.3 1661.97  4941.8 1659.83
  4957.8 1659.07    4979 1656.78  5030.2 1655.51  5030.7 1655.01    5042 1655.01
  5042.5 1655.51  5045.9 1657.03  5055.6 1659.12  5058.8 1660.82  5065.2 1662.31
    5078 1663.58    5114 1664.74  5167.2 1664.91  5183.9 1663.51  5253.8 1666.33
  5291.1    1668  5300.4 1669.27  5315.1 1670.11  5328.3 1669.46  5343.9 1670.04
  5372.8 1671.92  5382.4 1673.82  5391.2 1674.08  5398.4 1675.04  5422.9 1674.84
#Mann= 5 ,-1 , 0
  4854.3    .035       0  4941.8      .1       0  5030.2     .05       0
  5042.5      .1       0  5253.8    .035       0
Bank Sta=5030.2,5042.5
XS Rating Curve= 0 ,0
Exp/Cntr=0.3,0.1

Type RM Length L Ch R = 1 ,14498   ,341,341,341
BEGIN DESCRIPTION:
Camping Meeting Creek 26.0
END DESCRIPTION:
XS GIS Cut Line= 3
      1919424.98     13918824.99        1919125.       13918675.
      1918525.01     13918175.01
#Sta/Elev= 30
  4665.1  1676.2  4775.6 1674.65  4819.2 1669.67  4829.3 1664.16  4886.3 1664.38
  4906.4 1661.96  4963.4  1659.8  4976.3  1657.2  4994.2 1658.16  4998.7 1657.14
  4998.8 1655.71  4999.3 1655.21  5011.6 1655.71  5046.3 1656.01  5097.9 1657.31
  5111.4  1656.2  5123.9 1658.31  5184.9 1662.54  5232.8 1670.05  5298.9 1669.89
  5354.2 1673.58  5386.2 1673.76  5567.3 1684.07  5603.1 1687.23  5628.2 1691.41
  5635.4 1697.01  5671.3 1699.31  5718.5 1699.96  5735.5 1713.71  5781.5  1725.3
#Mann= 7 ,-1 , 0
  4665.1    .035       0  4998.8    .035       0  5011.6    .035       0
  5046.3      .1       0  5123.9    .035       0  5603.1    .063       0
  5671.3      .1       0
Bank Sta=4998.8,5011.6
XS Rating Curve= 0 ,0
Exp/Cntr=0.3,0.1

Type RM Length L Ch R = 1 ,14157   ,564,564,564
BEGIN DESCRIPTION:
Camping Meeting Creek 25.0
END DESCRIPTION:
XS GIS Cut Line= 3
        1919425.       13918625.      1919328.48     13918431.35
      1918925.01     13917925.01
#Sta/Elev= 30
  4740.1 1672.73  4770.4 1672.28  4777.1 1669.24  4793.6  1666.4  4854.1 1660.85
  4875.5    1655  4896.2 1651.97    4927  1651.3  4936.4 1649.82  4979.5 1649.44
    4980 1648.94  4992.4 1649.44  5009.4 1654.37  5058.5 1659.84  5090.5 1660.14
  5099.1 1662.01  5118.3 1663.21  5263.4 1666.88  5342.5 1672.43  5351.7 1674.67
  5383.9 1686.92  5455.4 1698.71    5466 1701.83    5481 1708.59    5494 1712.31
  5519.4 1713.25  5525.8 1714.45  5538.6 1720.06  5560.9 1723.82  5603.9 1725.75
#Mann= 3 ,-1 , 0
  4740.1    .035       0  4979.5    .035       0  4992.4    .035       0
Bank Sta=4979.5,4992.4
XS Rating Curve= 0 ,0
Exp/Cntr=0.3,0.1

Type RM Length L Ch R = 1 ,13593   ,307,307,307
BEGIN DESCRIPTION:
Camping Meeting Creek 24.0
END DESCRIPTION:
XS GIS Cut Line= 3
      1919824.99     13918874.96        1919625.       13918075.
      1919175.01     13917775.01
#Sta/Elev= 30
    4171 1672.86  4263.4  1670.3  4288.2 1670.95  4403.9 1667.25  4473.2 1664.73
  4535.6 1664.53  4690.9 1660.85  4795.3 1661.06  4876.5 1657.44    4885 1655.14
  4897.1 1649.58  4897.6 1649.08    4910 1649.58  4941.7  1649.8  5014.7 1650.21
  5032.1  1652.3  5081.8 1653.72  5116.8 1655.76  5134.8 1660.47  5183.5  1659.2
  5343.6 1668.12  5354.8 1671.45  5365.6 1677.97  5378.2 1682.43  5407.9 1690.61
  5440.9 1695.33  5467.4 1702.09  5488.2 1705.39  5492.8 1713.79  5536.4 1714.11
#Mann= 6 ,-1 , 0
    4171    .063       0  4403.9    .035       0  4897.1     .05       0
    4910    .035       0  4941.7      .1       0  5081.8    .035       0
Bank Sta=4897.1,4910
XS Rating Curve= 0 ,0
Exp/Cntr=0.3,0.1

Type RM Length L Ch R = 1 ,13286   ,670,670,670
BEGIN DESCRIPTION:
Camping Meeting Creek 23.1
END DESCRIPTION:
XS GIS Cut Line= 4
      1919941.65     13918555.72      1919927.07     13917993.89
      1919737.42     13917774.49      1919401.62     13917661.88
#Sta/Elev= 30
  4210.4 1662.62  4371.1 1658.71    4614 1656.27  4735.9 1655.73  4824.6  1656.7
  4875.6  1655.9  4901.1 1654.97  4907.5 1653.41  4913.9 1649.43  4922.4 1648.17
    4933 1648.97  4964.4 1648.53  4974.7 1648.39    5018 1647.78  5018.5 1647.28
  5030.9 1647.78  5035.3 1650.62  5041.5 1651.78  5042.9 1654.35  5044.5 1655.68
  5047.9 1654.09  5056.4 1653.34  5138.7 1658.17  5167.1 1661.88  5195.6 1659.81
  5220.9 1663.44  5284.2 1665.88  5290.3  1667.3  5385.5 1676.85  5416.6 1682.72
#Mann= 6 ,-1 , 0
  4210.4    .063       0  4371.1    .035       0  4964.4      .1       0
  4974.7    .035       0    5018    .035       0  5030.9    .035       0
Bank Sta=5018,5030.9
XS Rating Curve= 0 ,0
Exp/Cntr=0.3,0.1

Type RM Length L Ch R = 1 ,12616   ,384,384,384
BEGIN DESCRIPTION:
Camping Meeting Creek 23.0
END DESCRIPTION:
XS GIS Cut Line= 4
      1920060.65      13918599.4      1920237.13     13917700.66
      1920238.02     13917520.34        1920025.       13917375.
#Sta/Elev= 30
  4157.5 1662.42    4252 1659.61  4374.7 1657.31  4426.6 1657.33  4598.2  1654.8
  4628.8  1653.3  4662.1 1653.38  4671.2 1651.86  4711.3 1650.92  4839.4 1648.85
  4865.9 1646.05  4897.5 1644.67  4915.8 1642.76  4937.4 1637.95  4952.8 1636.21
  4956.5 1634.68    4957 1634.18  4969.5 1634.68  4989.2 1636.26  5011.5 1636.45
  5019.8 1641.56    5032 1645.89  5042.2  1648.1  5068.7 1649.76  5083.8 1653.77
  5333.5 1655.69  5355.3 1656.72    5378 1655.78  5442.2 1655.72  5511.6 1657.26
#Mann= 7 ,-1 , 0
  4157.5    .035       0    4252    .063       0  4426.6    .035       0
  4598.2    .063       0  4711.3    .035       0  4956.5    .035       0
  4969.5    .035       0
Bank Sta=4956.5,4969.5
XS Rating Curve= 0 ,0
Exp/Cntr=0.3,0.1

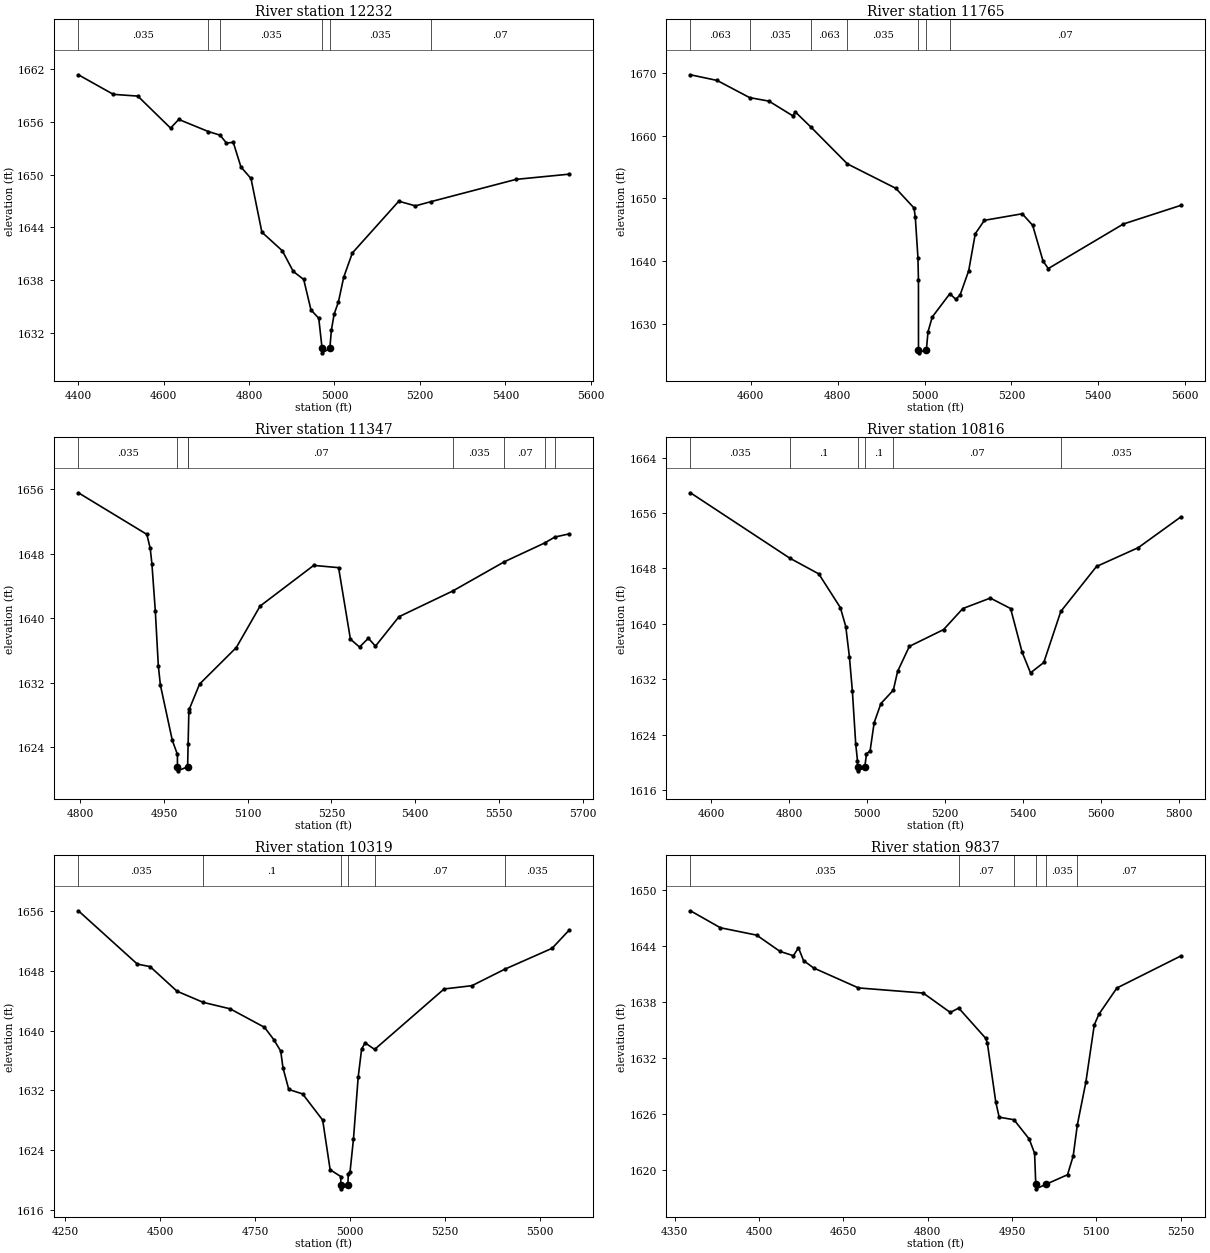
Type RM Length L Ch R = 1 ,12232   ,467,467,467
BEGIN DESCRIPTION:
Camping Meeting Creek 22.0
END DESCRIPTION:
XS GIS Cut Line= 3
      1920268.74     13918595.19        1920475.       13918025.
      1920840.45     13917625.34
#Sta/Elev= 30
  4400.7 1661.38  4482.5 1659.15  4539.8 1658.95  4616.5  1655.3  4635.6 1656.29
    4705 1654.91  4732.2  1654.5  4747.3  1653.6  4763.2 1653.68  4781.2 1650.87
  4804.7 1649.56  4830.2 1643.44  4878.1 1641.32  4903.6 1638.97  4928.1 1638.05
  4945.1 1634.58  4963.3 1633.63  4971.1 1630.19  4971.6 1629.69  4989.2 1630.19
  4992.9 1632.29  4999.3  1634.1  5009.4  1635.5  5021.6 1638.29  5041.9 1641.07
  5150.6 1646.97  5189.5 1646.44  5225.1 1646.91  5425.1 1649.46  5548.6 1650.05
#Mann= 6 ,-1 , 0
  4400.7    .035       0    4705    .063       0  4732.2    .035       0
  4971.1    .035       0  4989.2    .035       0  5225.1     .07       0
Bank Sta=4971.1,4989.2
XS Rating Curve= 0 ,0
Exp/Cntr=0.3,0.1

Type RM Length L Ch R = 1 ,11765   ,418,418,418
BEGIN DESCRIPTION:
Camping Meeting Creek 21.0
END DESCRIPTION:
XS GIS Cut Line= 3
      1920800.82     13918813.67        1920825.       13918275.
      1920847.97     13917685.16
#Sta/Elev= 30
  4460.9 1669.67  4522.3 1668.77  4597.2 1666.04  4641.7 1665.48  4696.5 1663.15
  4702.5 1663.76    4739 1661.31  4822.4  1655.5  4933.8 1651.62  4975.8 1648.49
  4978.8 1646.99  4984.8 1640.61    4986 1637.01  4986.1 1625.96  4986.6 1625.46
  5004.3 1625.96    5008  1628.8  5017.8 1631.16  5058.3 1634.86  5071.9 1633.98
  5081.8 1634.63  5101.7 1638.51  5116.9  1644.4  5137.9 1646.53    5225 1647.57
    5249 1645.74    5273 1640.04    5285 1638.86  5457.8 1645.94  5590.4 1648.91
#Mann= 7 ,-1 , 0
  4460.9    .063       0  4597.2    .035       0    4739    .063       0
  4822.4    .035       0  4986.1    .035       0  5004.3    .035       0
  5058.3     .07       0
#Block Obstruct= 2 , 0
                         5206.79         1647.25
Bank Sta=4986.1,5004.3
XS Rating Curve= 0 ,0
Exp/Cntr=0.3,0.1

Type RM Length L Ch R = 1 ,11347   ,531,531,531
BEGIN DESCRIPTION:
Camping Meeting Creek 20.0
END DESCRIPTION:
XS GIS Cut Line= 3
        1921175.     13918375.02       1921212.3     13918168.11
      1920989.12     13917537.59
#Sta/Elev= 30
  4796.4 1655.57  4919.1 1650.41  4925.2 1648.66  4928.2 1646.76  4934.3 1640.91
  4939.7  1634.1  4943.4 1631.72  4964.8 1624.84  4973.9 1623.11    4974 1621.57
  4974.5 1621.07  4992.2 1621.57  4993.1 1624.35  4994.4 1628.37  4995.3 1628.74
  5013.7 1631.84  5079.5 1636.37  5122.1 1641.51  5218.2 1646.56  5262.8 1646.28
    5284 1637.41  5300.3 1636.43  5316.2 1637.52  5328.9 1636.54    5371 1640.19
  5467.6 1643.39  5559.9 1647.01  5632.1 1649.34  5650.5 1650.08  5675.5 1650.46
#Mann= 8 ,-1 , 0
  4796.4    .035       0    4974     .05       0  4992.2    .035       0
  4993.1     .07       0  5467.6    .035       0  5559.9     .07       0
  5632.1    .035       0  5650.5     .07       0
#Block Obstruct= 2 , 0
                         5238.96         1646.67
Bank Sta=4974,4992.2
XS Rating Curve= 0 ,0
Exp/Cntr=0.3,0.1

Type RM Length L Ch R = 1 ,10816   ,497,497,497
BEGIN DESCRIPTION:
Camping Meeting Creek 19.0
END DESCRIPTION:
XS GIS Cut Line= 3
      1921793.97     13918353.02        1921625.       13917925.
      1921151.61     13917280.92
#Sta/Elev= 30
  4546.6 1658.91  4801.2 1649.49  4876.2  1647.2  4931.7 1642.32  4945.5  1639.6
  4954.8 1635.24  4962.4 1630.33    4971 1622.69  4975.6  1620.2  4975.7 1619.27
  4976.2 1618.77  4994.2 1619.27  4998.7 1621.23  5007.9 1621.63  5018.4 1625.72
  5035.8 1628.49  5067.6 1630.41  5078.7 1633.14  5108.8 1636.74  5196.7 1639.16
  5246.1  1642.2  5316.7 1643.71  5368.8  1642.2  5398.3 1635.91  5419.9 1632.91
    5454 1634.41  5497.7 1641.78  5589.4 1648.27  5696.7 1650.99  5806.1 1655.43
#Mann= 6 ,-1 , 0
  4546.6    .035       0  4801.2      .1       0  4975.7     .05       0
  4994.2      .1       0  5067.6     .07       0  5497.7    .035       0
#Block Obstruct= 2 , 0
                         5311.09         1643.73
Bank Sta=4975.7,4994.2
XS Rating Curve= 0 ,0
Exp/Cntr=0.3,0.1

Type RM Length L Ch R = 1 ,10319   ,482,482,482
BEGIN DESCRIPTION:
Camping Meeting Creek 18.0
END DESCRIPTION:
XS GIS Cut Line= 3
      1922098.61     13918284.34        1921975.       13917575.
      1921862.96     13917014.01
#Sta/Elev= 30
  4284.4 1656.07  4439.8 1648.92  4473.3 1648.59  4544.2 1645.29  4613.5 1643.79
  4684.2 1642.93  4774.7 1640.45  4799.1 1638.81  4817.4 1637.27  4823.5 1635.01
  4838.7 1632.12  4875.2 1631.52    4928 1628.01  4947.7 1621.36  4975.7 1620.45
  4975.8  1619.3  4976.3  1618.8  4994.3  1619.3  4995.6 1620.82  5000.1 1621.08
  5009.2 1625.52  5021.5 1633.74  5030.6 1637.55  5039.8 1638.36  5064.9 1637.49
  5247.9 1645.59  5321.3 1646.03  5407.4 1648.23  5532.4 1651.04  5576.5 1653.43
#Mann= 6 ,-1 , 0
  4284.4    .035       0  4613.5      .1       0  4975.8     .05       0
  4994.3      .1       0  5064.9     .07       0  5407.4    .035       0
Bank Sta=4975.8,4994.3
XS Rating Curve= 0 ,0
Exp/Cntr=0.3,0.1

Type RM Length L Ch R = 1 ,9837    ,466,466,466
BEGIN DESCRIPTION:
Camping Meeting Creek 17.0
END DESCRIPTION:
XS GIS Cut Line= 3
      1922411.12     13918197.44        1922425.       13917575.
      1922274.99     13917374.99
#Sta/Elev= 30
  4377.8 1647.79  4431.1 1645.97  4495.6 1645.18    4537 1643.44    4561 1642.97
    4570 1643.82    4579 1642.45    4597 1641.66  4676.7 1639.52    4792 1638.97
  4840.1 1636.89  4855.1 1637.36  4903.1 1634.12  4906.1 1633.59  4921.1 1627.27
  4927.1 1625.66  4953.4 1625.39  4980.5 1623.32  4990.1 1621.79  4992.2 1618.48
  4992.7 1617.98  5010.8 1618.48  5048.7 1619.49  5058.8  1621.5  5066.1 1624.82
  5081.3 1629.41  5096.3 1635.55  5104.4 1636.69  5136.5 1639.51  5250.4 1642.95
#Mann= 6 ,-1 , 0
  4377.8    .035       0  4855.1     .07       0  4953.4    .035       0
  4992.2    .035       0  5010.8    .035       0  5066.1     .07       0
Bank Sta=4992.2,5010.8
XS Rating Curve= 0 ,0
Exp/Cntr=0.3,0.1

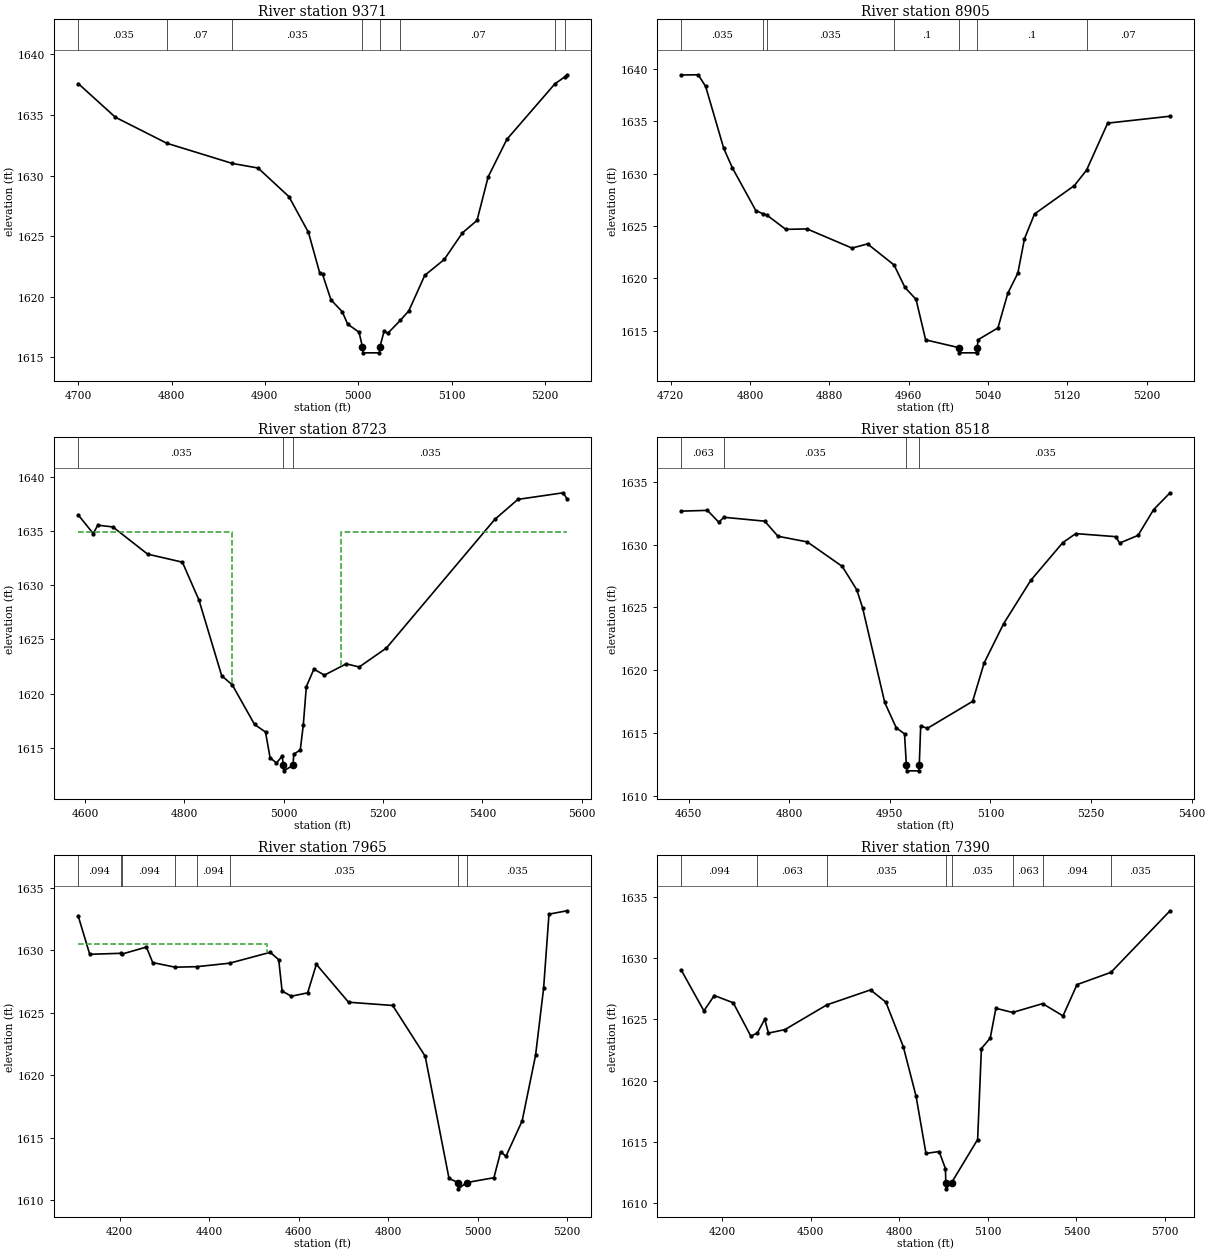
Type RM Length L Ch R = 1 ,9371    ,466,466,466
BEGIN DESCRIPTION:
Camping Meeting Creek 16.0
END DESCRIPTION:
XS GIS Cut Line= 3
        1922875.     13917924.99        1922875.       13917625.
        1922775.     13917424.99
#Sta/Elev= 30
  4700.1 1637.58  4739.8 1634.81  4795.1 1632.66  4865.1    1631  4892.7 1630.62
  4925.8 1628.26  4946.7 1625.31  4958.8 1621.96  4961.8 1621.85  4970.8 1619.75
  4982.9 1618.77  4988.7 1617.75  5000.9 1617.08  5004.5 1615.88    5005 1615.38
  5022.8 1615.38  5023.3 1615.88  5027.7 1617.16  5031.8    1617    5045 1618.05
  5054.2 1618.84  5071.3 1621.77  5092.2 1623.08  5111.6 1625.27  5127.3  1626.3
  5139.2 1629.89  5159.3 1632.99  5210.7 1637.56  5221.2 1638.13  5223.7 1638.31
#Mann= 8 ,-1 , 0
  4700.1    .035       0  4795.1     .07       0  4865.1    .035       0
  5004.5    .035       0  5023.3    .035       0    5045     .07       0
  5210.7    .035       0  5221.2     .07       0
Bank Sta=5004.5,5023.3
XS Rating Curve= 0 ,0
Exp/Cntr=0.3,0.1

Type RM Length L Ch R = 1 ,8905    ,182,182,182
BEGIN DESCRIPTION:
Camping Meeting Creek 15.0
END DESCRIPTION:
XS GIS Cut Line= 3
      1923224.99     13917925.04        1923325.       13917675.
        1923225.       13917475.
#Sta/Elev= 30
  4730.8 1639.44  4747.8 1639.46  4755.3 1638.35  4773.6 1632.42  4782.3 1630.56
  4805.9 1626.49  4813.1 1626.18  4816.8 1626.07  4836.1 1624.69  4857.6 1624.73
  4902.9  1622.9  4918.6  1623.3  4945.4 1621.28  4956.3 1619.14  4967.5    1618
  4977.2 1614.13  5010.5 1613.39    5011 1612.89  5028.8 1612.89  5029.3 1613.39
    5030 1614.14  5050.1 1615.27  5060.1 1618.59  5070.2 1620.51  5076.9  1623.8
    5087 1626.16  5127.2 1628.87  5139.5 1630.35  5160.8 1634.84  5223.7  1635.5
#Mann= 7 ,-1 , 0
  4730.8    .035       0  4813.1     .07       0  4816.8    .035       0
  4945.4      .1       0  5010.5     .05       0  5029.3      .1       0
  5139.5     .07       0
Bank Sta=5010.5,5029.3
XS Rating Curve= 0 ,0
Exp/Cntr=0.3,0.1

Type RM Length L Ch R = 1 ,8723    ,205,205,205
BEGIN DESCRIPTION:
Mapping XS 52be108d
END DESCRIPTION:
XS GIS Cut Line= 2
      1923437.39     13918082.95      1923602.52      13917112.8
#Sta/Elev= 30
  4586.2 1636.47  4616.3 1634.76  4625.4 1635.53  4655.8 1635.37  4725.8 1632.86
  4795.8 1632.12  4829.3 1628.61    4875 1621.64  4896.3  1620.8  4941.1 1617.15
  4963.2 1616.45  4972.4 1614.08  4985.3 1613.59  4996.7 1614.23  4999.2 1613.37
  4999.7 1612.87  5018.5 1613.37  5020.1  1614.4  5033.2  1614.8  5039.3 1617.11
  5045.4 1620.64  5060.6 1622.25  5081.9  1621.7  5125.7 1622.74  5151.9 1622.45
  5206.7  1624.2  5424.8 1636.06  5471.4 1637.91  5562.7 1638.52  5570.3 1637.96
#Mann= 3 ,-1 , 0
  4586.2    .035       0  4999.2    .035       0  5018.5    .035       0
#XS Ineff= 2 , 0
          4896.3 1634.91 5115.68         1634.91
Permanent Ineff=
       F       F
Bank Sta=4999.2,5018.5
XS Rating Curve= 0 ,0
Exp/Cntr=0.3,0.1

Type RM Length L Ch R = 1 ,8518    ,553,553,553
BEGIN DESCRIPTION:
Camping Meeting Creek 14.0
END DESCRIPTION:
XS GIS Cut Line= 3
      1923624.99     13918025.04      1923720.28     13917643.78
      1923824.99     13917325.03
#Sta/Elev= 30
  4639.2 1632.67  4678.1 1632.73    4695 1631.79  4702.7 1632.18  4763.5 1631.87
  4783.2 1630.67  4826.9 1630.22  4879.1 1628.27  4900.8  1626.4  4909.4 1624.97
  4942.4 1617.44  4959.5 1615.43  4971.9 1614.94  4974.6  1612.5  4975.1    1612
  4993.4    1612  4993.9  1612.5    4996 1615.58  5005.9 1615.38  5073.4 1617.53
  5090.6 1620.59  5119.6 1623.71  5160.1 1627.16  5207.9 1630.17  5227.2 1630.88
  5286.4 1630.64  5292.7 1630.13    5320 1630.74  5343.2 1632.79  5367.7 1634.13
#Mann= 4 ,-1 , 0
  4639.2    .063       0  4702.7    .035       0  4974.6    .035       0
  4993.9    .035       0
Bank Sta=4974.6,4993.9
XS Rating Curve= 0 ,0
Exp/Cntr=0.3,0.1

Type RM Length L Ch R = 1 ,7965    ,575,575,575
BEGIN DESCRIPTION:
Camping Meeting Creek 13.0
END DESCRIPTION:
XS GIS Cut Line= 3
      1923675.35     13918328.39        1924225.       13917625.
        1924225.     13917424.98
#Sta/Elev= 30
  4107.3  1632.7  4132.9 1629.66    4202 1629.74  4205.1 1629.68  4259.6 1630.24
  4273.7    1629  4323.8 1628.63  4372.1 1628.67  4445.6 1628.95  4536.4 1629.82
  4555.4 1629.23    4563 1626.72  4583.8 1626.31  4620.1 1626.58  4639.6 1628.86
  4711.5 1625.83  4810.2 1625.57  4882.9 1621.51  4936.2 1611.74  4956.4 1611.41
  4956.9 1610.91  4975.7 1611.41  5036.6  1611.8  5051.6 1613.86  5063.6 1613.52
  5099.7 1616.34  5129.7 1621.59  5147.7 1626.95  5159.7 1632.87    5200 1633.14
#Mann= 8 ,-1 , 0
  4107.3    .094       0    4202    .035       0  4205.1    .094       0
  4323.8    .063       0  4372.1    .094       0  4445.6    .035       0
  4956.4    .035       0  4975.7    .035       0
#XS Ineff= 2 , 0
         4529.87 1630.51
Permanent Ineff=
       F       F
Bank Sta=4956.4,4975.7
XS Rating Curve= 0 ,0
Exp/Cntr=0.3,0.1

Type RM Length L Ch R = 1 ,7390    ,188,188,188
BEGIN DESCRIPTION:
Camping Meeting Creek 12.2
END DESCRIPTION:
XS GIS Cut Line= 4
       1923922.6     13918544.06      1924633.55     13917826.23
       1924707.6     13917573.45      1924657.07     13917271.57
#Sta/Elev= 30
 4062.94 1629.01  4139.3  1625.7  4174.5 1626.95  4238.5 1626.36  4298.1 1623.64
  4320.5  1623.9    4345 1625.02  4357.8 1623.89  4413.2 1624.17  4555.4 1626.19
  4703.1 1627.41    4755 1626.41    4814 1622.78  4857.1 1618.75  4890.7 1614.08
  4935.3 1614.23  4956.6 1612.84  4957.8 1611.69  4958.3 1611.19  4977.2 1611.69
  5065.5 1615.21  5078.3 1622.63  5108.1 1623.48  5127.3 1625.91  5183.9 1625.57
  5285.4 1626.29  5354.4 1625.29  5401.7 1627.84  5516.6 1628.84  5716.6 1633.86
#Mann= 8 ,-1 , 0
 4062.94    .094       0  4320.5    .063       0  4555.4    .035       0
  4957.8    .035       0  4977.2    .035       0  5183.9    .063       0
  5285.4    .094       0  5516.6    .035       0
Bank Sta=4957.8,4977.2
XS Rating Curve= 0 ,0
Exp/Cntr=0.3,0.1

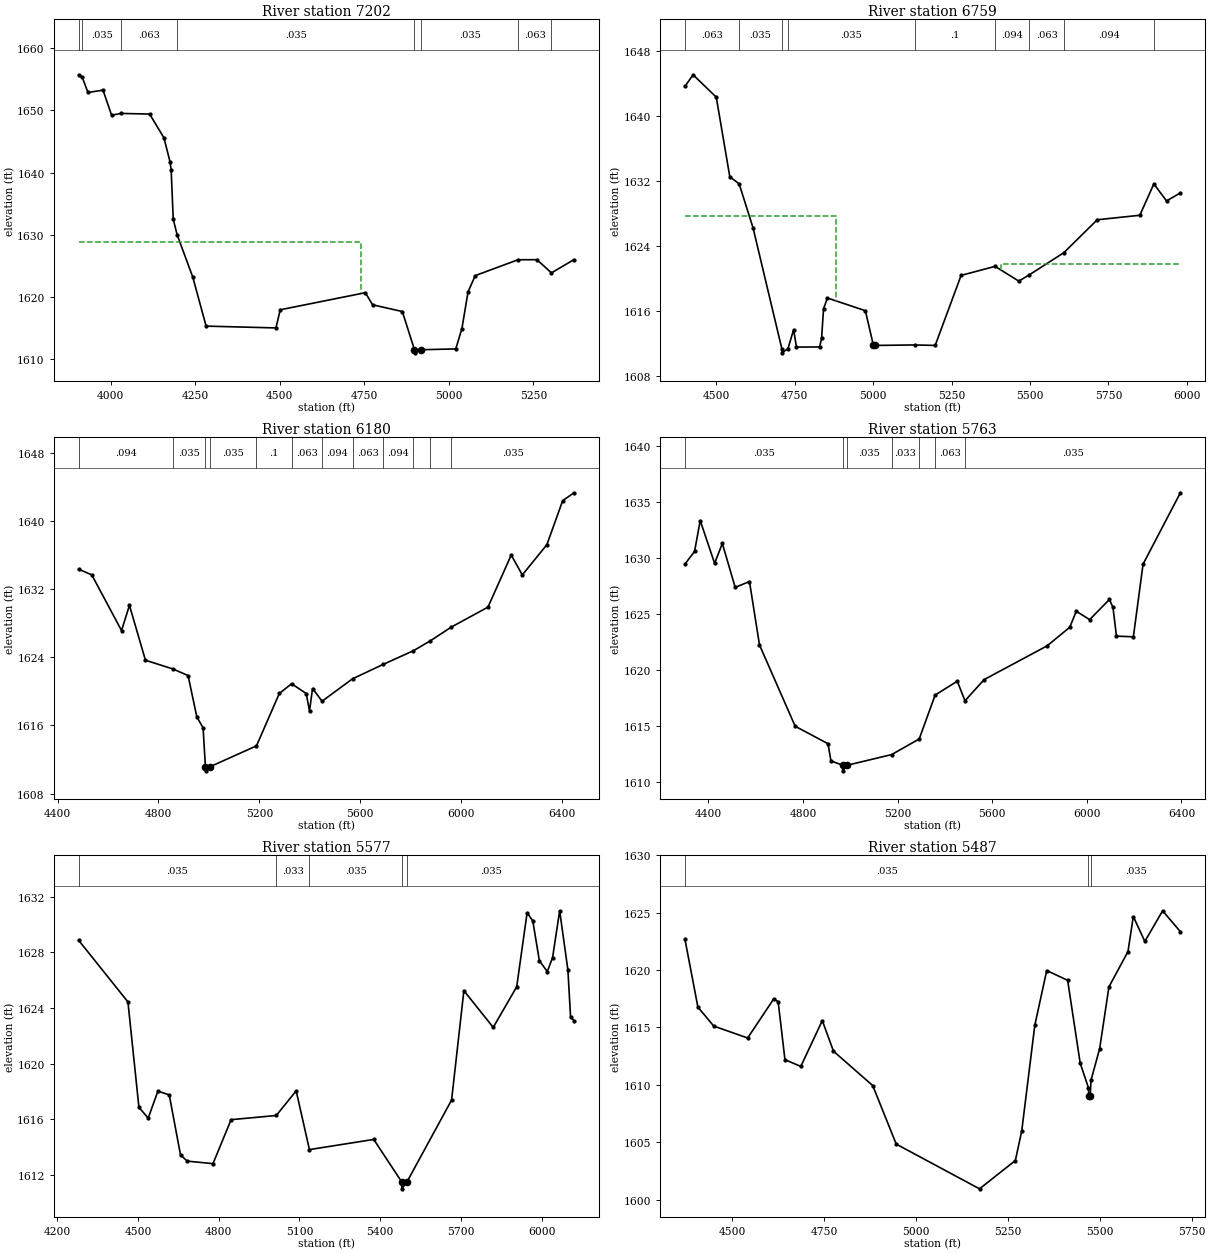
Type RM Length L Ch R = 1 ,7202    ,443,443,443
BEGIN DESCRIPTION:
Mapping XS b65b339a
END DESCRIPTION:
XS GIS Cut Line= 2
      1924524.85     13919076.58      1924753.01     13917629.86
#Sta/Elev= 30
  3905.6 1655.74  3916.5 1655.32  3933.2 1652.89  3977.7 1653.27  4003.1 1649.22
    4030 1649.52  4115.5 1649.42  4157.9 1645.58  4176.2 1641.64  4179.2 1640.39
  4185.3  1632.5  4196.6 1630.03    4243 1623.19  4282.5 1615.29    4489    1615
  4501.6 1617.92  4753.2 1620.67  4774.6 1618.72  4862.6 1617.64  4898.4 1611.49
  4898.9 1610.99  4917.8 1611.49  5020.5 1611.62  5038.7  1614.9  5056.9 1620.81
  5078.2 1623.42  5204.5 1625.97  5260.4 1625.98  5303.5 1623.86  5370.2    1626
#Mann= 8 ,-1 , 0
  3905.6    .063       0  3916.5    .035       0    4030    .063       0
  4196.6    .035       0  4898.4    .035       0  4917.8    .035       0
  5204.5    .063       0  5303.5    .094       0
#XS Ineff= 2 , 0
         4741.46 1628.76
Permanent Ineff=
       F       F
Bank Sta=4898.4,4917.8
XS Rating Curve= 0 ,0
Exp/Cntr=0.3,0.1

Type RM Length L Ch R = 1 ,6759    ,579,579,579
BEGIN DESCRIPTION:
Camping Meeting Creek 12.1
END DESCRIPTION:
XS GIS Cut Line= 4
       1924774.2     13918846.42      1924898.19     13918309.54
      1925014.25     13917977.21      1924736.39     13917362.08
#Sta/Elev= 30
    4401 1643.62  4426.8 1645.05  4500.7  1642.3  4543.8 1632.52  4573.6 1631.64
  4617.7 1626.26  4709.6 1611.37  4710.1 1610.87    4729 1611.37  4747.1 1613.72
  4756.2 1611.58  4830.1 1611.59  4836.3 1612.71  4842.4 1616.29  4854.8 1617.61
  4975.7 1616.05    5001 1611.82  5007.4 1611.78    5133 1611.84    5198 1611.78
  5280.6 1620.39  5388.8  1621.5  5464.3 1619.69  5498.3 1620.47  5607.8 1623.18
  5714.3 1627.23  5849.8 1627.78  5894.5 1631.64  5934.9 1629.54    5979 1630.53
#Mann= 9 ,-1 , 0
    4401    .063       0  4573.6    .035       0  4709.6    .035       0
    4729    .035       0    5133      .1       0  5388.8    .094       0
  5498.3    .063       0  5607.8    .094       0  5894.5    .035       0
#XS Ineff= 2 , 0
         4882.72 1627.64 5408.59         1621.74
Permanent Ineff=
       F       F
Bank Sta=5001,5007.4
XS Rating Curve= 0 ,0
Exp/Cntr=0.3,0.1

Type RM Length L Ch R = 1 ,6180    ,417,417,417
BEGIN DESCRIPTION:
Camping Meeting Creek 12.0
END DESCRIPTION:
XS GIS Cut Line= 3
        1925275.     13918775.01        1925425.       13918275.
      1924625.02     13917075.04
#Sta/Elev= 30
  4483.6 1634.32  4535.7 1633.66  4653.7 1627.12  4685.1 1630.08  4748.5 1623.64
  4857.9 1622.61  4917.6 1621.84  4952.1    1617  4977.1  1615.7  4986.2 1611.16
  4986.7 1610.66  5005.8 1611.16  5188.7 1613.59  5279.3 1619.74    5328 1620.88
  5386.1 1619.73    5399 1617.68    5411 1620.32  5448.8 1618.83  5569.5 1621.46
  5690.3 1623.14  5811.1 1624.76  5878.3 1625.92  5961.2 1627.53  6106.5 1629.87
  6198.7 1635.98  6242.7 1633.65  6340.1  1637.2  6402.8 1642.37  6447.8 1643.29
#Mann= 12 ,-1 , 0
  4483.6    .094       0  4857.9    .035       0  4986.2    .035       0
  5005.8    .035       0  5188.7      .1       0    5328    .063       0
  5448.8    .094       0  5569.5    .063       0  5690.3    .094       0
  5811.1    .063       0  5878.3    .094       0  5961.2    .035       0
#XS Ineff= 2 , 0
                         5328.67         1620.83
Permanent Ineff=
       F       F
Bank Sta=4986.2,5005.8
XS Rating Curve= 0 ,0
Exp/Cntr=0.3,0.1

Type RM Length L Ch R = 1 ,5763    ,186,186,186
BEGIN DESCRIPTION:
Camping Meeting Creek 11.0
END DESCRIPTION:
XS GIS Cut Line= 3
      1925766.01     13918837.37      1925834.96     13918210.09
      1924998.16     13917009.62
#Sta/Elev= 30
  4301.1 1629.46  4341.7 1630.59  4365.6 1633.34  4426.5 1629.52  4459.1  1631.3
  4513.5 1627.38  4573.8  1627.9  4616.1 1622.25    4767 1614.99  4905.8 1613.43
  4918.2  1611.9  4967.5 1611.51    4968 1611.01  4987.1 1611.51  5174.8 1612.46
  5291.3 1613.85  5358.7 1617.77  5452.4 1619.01  5484.8 1617.26  5565.8 1619.15
  5832.7 1622.17  5927.8 1623.82  5955.4 1625.25  6011.9  1624.5  6095.5  1626.3
  6110.5  1625.6  6125.3 1623.03  6196.8 1622.97  6237.7 1629.45  6395.5 1635.82
#Mann= 7 ,-1 , 0
  4301.1    .035       0  4967.5    .035       0  4987.1    .035       0
  5174.8    .033       0  5291.3    .035       0  5358.7    .063       0
  5484.8    .035       0
Bank Sta=4967.5,4987.1
XS Rating Curve= 0 ,0
Exp/Cntr=0.3,0.1

Type RM Length L Ch R = 1 ,5577    ,90,90,90
BEGIN DESCRIPTION:
Camp Meeting Creek 10.1
END DESCRIPTION:
XS GIS Cut Line= 4
      1926030.65     13918694.96      1925992.46      13918156.8
      1925784.13     13917830.41      1925311.91     13917049.16
#Sta/Elev= 30
  4279.9 1628.87    4463 1624.44  4503.8 1616.87  4538.2 1616.09  4574.3 1618.03
  4616.4 1617.76  4658.3 1613.44  4683.5    1613  4778.8 1612.82  4846.1 1615.98
  5013.7 1616.28  5087.7 1618.05  5136.9 1613.83  5375.7 1614.56  5479.5 1611.51
    5480 1611.01  5499.1 1611.51  5664.8 1617.39  5710.4 1625.25  5819.4 1622.61
  5906.6 1625.53  5945.2 1630.85  5966.3 1630.26  5990.8  1627.4  6020.2 1626.62
  6039.8 1627.63  6066.1 1630.99  6096.7 1626.73  6106.5 1623.39  6119.5 1623.09
#Mann= 5 ,-1 , 0
  4279.9    .035       0  5013.7    .033       0  5136.9    .035       0
  5479.5    .035       0  5499.1    .035       0
Bank Sta=5479.5,5499.1
XS Rating Curve= 0 ,0
Exp/Cntr=0.3,0.1

Type RM Length L Ch R = 1 ,5487    ,673,673,673
BEGIN DESCRIPTION:
Mapping XS 38c4f209
END DESCRIPTION:
XS GIS Cut Line= 3
      1926153.11     13918531.61      1926056.36      13918104.6
      1925592.06     13917322.12
#Sta/Elev= 30
  4371.7 1622.68  4406.9 1616.77    4450 1615.12  4542.2 1614.08    4613 1617.48
  4625.2 1617.25  4643.7 1612.19  4686.8  1611.6  4745.3  1615.6  4775.7 1612.93
  4882.5 1609.93  4946.4 1604.83    5173 1600.93  5270.5  1603.4  5287.8 1605.97
  5323.4 1615.19  5355.8 1619.96  5412.7 1619.11  5446.9 1611.88  5469.2 1609.75
  5470.4    1609 5474.28 1609.01  5476.2 1610.39  5499.8 1613.15    5525 1618.53
  5576.9 1621.62  5591.3 1624.67  5622.7  1622.5  5671.1 1625.17  5719.4 1623.35
#Mann= 3 ,-1 , 0
  4371.7    .035       0  5469.2    .035       0  5476.2    .035       0
#Block Obstruct= 2 , 0
          5296.5 1607.78
Bank Sta=5470.4,5474.28
XS Rating Curve= 0 ,0
Exp/Cntr=0.3,0.1