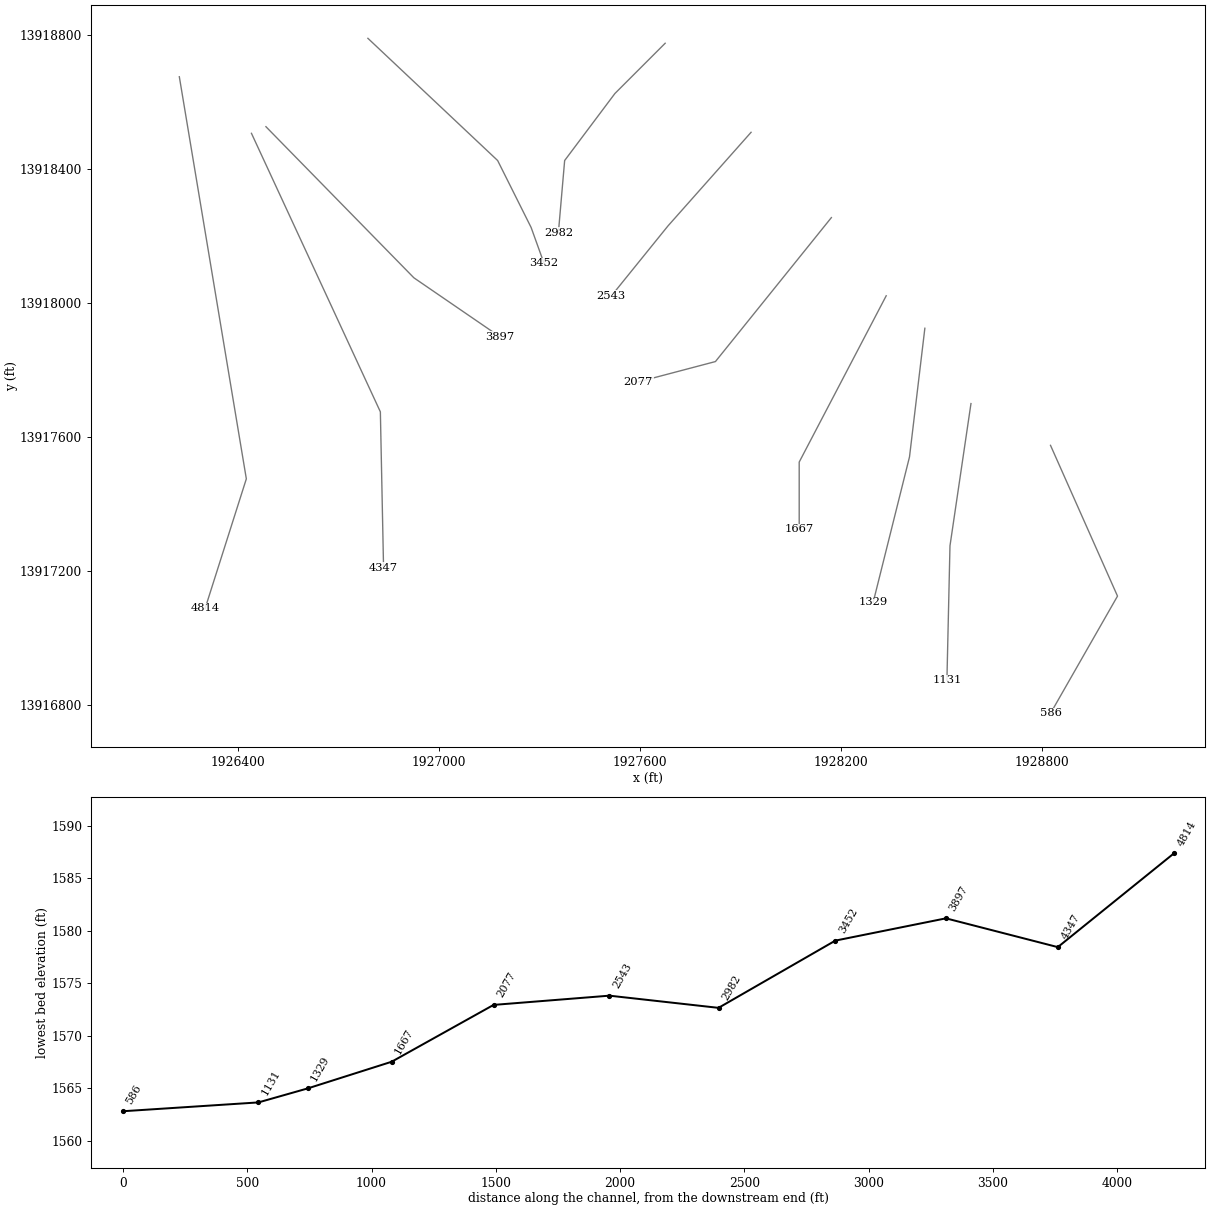
HEC-RAS study Camp Meeting Creek.prj: Camp Meeting Creek Base Level Engineering

--- Camp Meeting Creek.g01 (geometry) --- (continued)

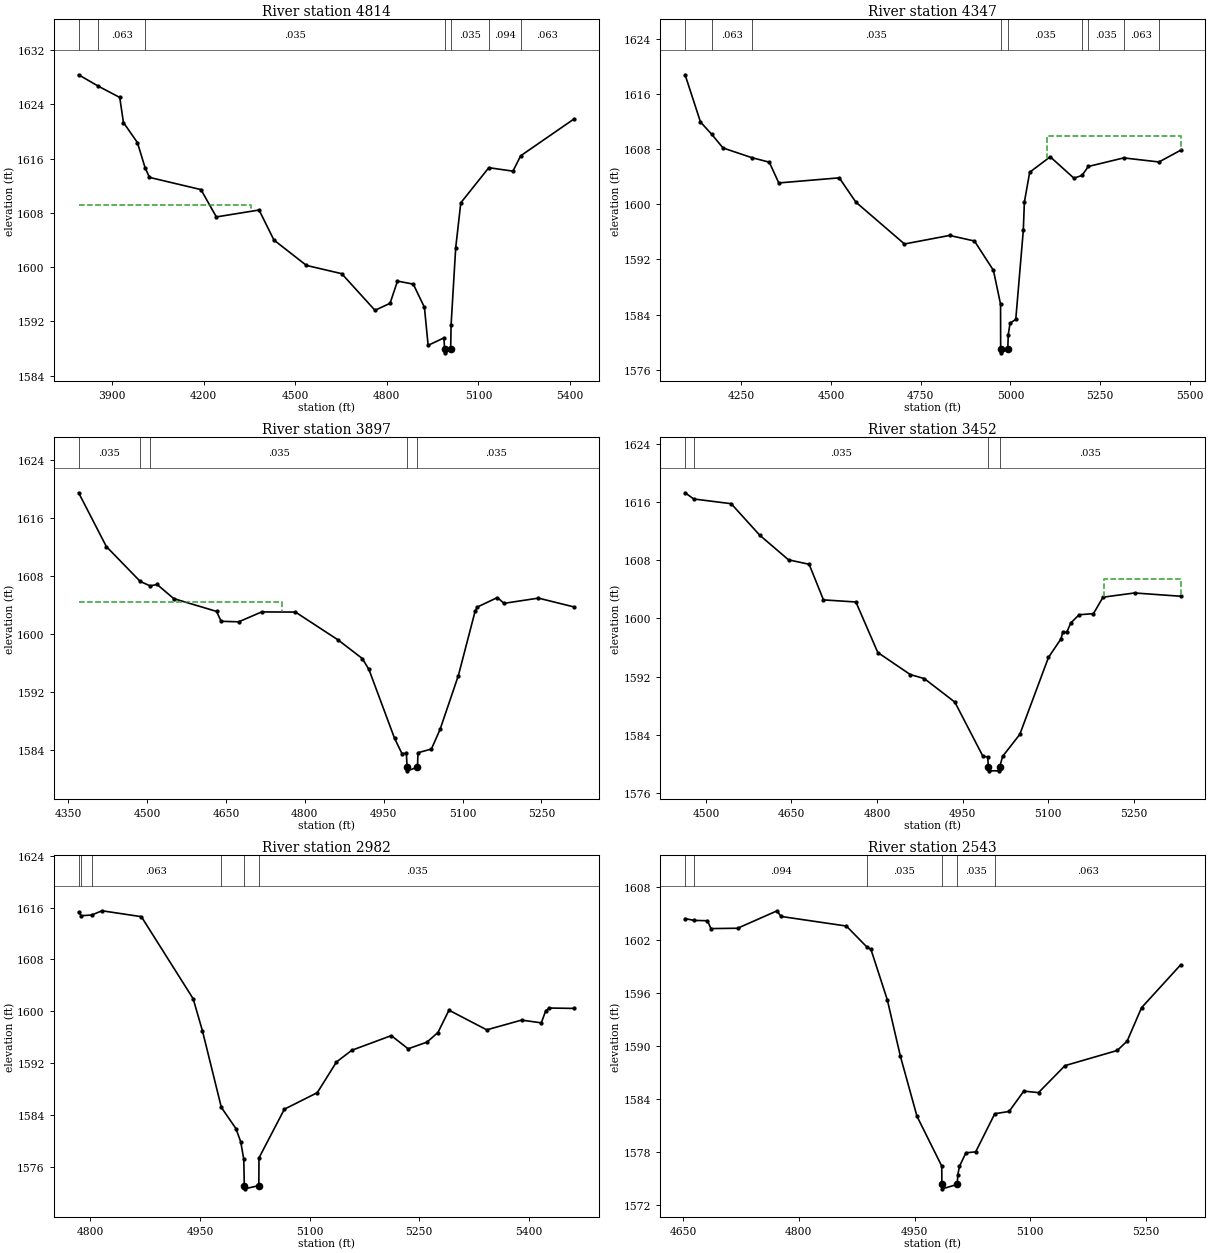
Type RM Length L Ch R = 1 ,4814    ,467,467,467
BEGIN DESCRIPTION:
Camping Meeting Creek 10.0
END DESCRIPTION:
XS GIS Cut Line= 3
      1926224.99     13918675.04        1926425.       13917475.
      1926301.99     13917088.18
#Sta/Elev= 30
    3791 1628.37  3854.2 1626.72  3925.6 1625.03  3937.7 1621.33  3983.4 1618.38
  4008.7 1614.65  4022.9 1613.24  4191.5 1611.44  4241.9 1607.41  4381.8 1608.43
  4430.5    1604  4536.9 1600.26  4652.5 1599.04  4761.3 1593.64  4810.6 1594.67
    4835 1597.95  4886.7  1597.5  4923.2 1594.08  4935.3 1588.48    4987 1589.57
  4989.3 1587.87  4989.8 1587.37  5009.1 1587.87  5010.5 1591.49  5025.6 1602.86
  5042.3 1609.49    5134 1614.67    5213 1614.16  5238.3 1616.42  5413.5 1621.87
#Mann= 7 ,-1 , 0
    3791    .035       0  3854.2    .063       0  4008.7    .035       0
  4989.3    .035       0  5009.1    .035       0    5134    .094       0
  5238.3    .063       0
#XS Ineff= 2 , 0
         4355.24 1609.14
Permanent Ineff=
       F       F
Bank Sta=4989.3,5009.1
XS Rating Curve= 0 ,0
Exp/Cntr=0.3,0.1

Type RM Length L Ch R = 1 ,4347    ,450,450,450
BEGIN DESCRIPTION:
Camping Meeting Creek 9.0
END DESCRIPTION:
XS GIS Cut Line= 3
      1926440.27     13918506.19        1926825.       13917675.
      1926834.54     13917209.91
#Sta/Elev= 30
  4093.1 1618.76    4136 1611.91    4167 1610.15  4198.8 1608.15  4278.2 1606.76
  4327.7 1606.09  4354.2 1603.08  4522.7 1603.82    4569  1600.3  4704.5 1594.23
  4830.2 1595.47  4899.6 1594.66  4952.5  1590.4  4972.3  1585.5  4972.6 1578.95
  4973.1 1578.45  4992.4 1578.95  4993.8 1581.09  4998.8 1582.75  5014.7  1583.3
  5035.7  1596.2  5038.7 1600.31  5053.5 1604.63  5110.7 1606.87  5176.8 1603.77
  5199.2 1604.17  5217.1 1605.47  5315.5 1606.71  5413.8 1606.12  5474.2 1607.82
#Mann= 9 ,-1 , 0
  4093.1    .035       0    4167    .063       0  4278.2    .035       0
  4972.6    .035       0  4992.4    .035       0  5199.2    .063       0
  5217.1    .035       0  5315.5    .063       0  5413.8    .094       0
#XS Ineff= 2 , 0
                          5101.3         1609.92
Permanent Ineff=
       F       F
Bank Sta=4972.6,4992.4
XS Rating Curve= 0 ,0
Exp/Cntr=0.3,0.1

Type RM Length L Ch R = 1 ,3897    ,445,445,445
BEGIN DESCRIPTION:
Camping Meeting Creek 8.0
END DESCRIPTION:
XS GIS Cut Line= 3
      1926483.47     13918525.98        1926925.       13918075.
      1927182.25      13917898.7
#Sta/Elev= 30
  4369.5 1619.44  4422.2 1612.05  4486.8 1607.24  4505.7 1606.63  4518.8 1606.83
  4550.5 1604.88    4632 1603.12  4640.6 1601.76  4674.2 1601.69  4717.8 1603.05
  4782.1 1603.03  4863.6 1599.18  4909.3 1596.64  4921.9 1595.14  4970.8 1585.64
  4984.8 1583.56  4993.2 1583.62  4994.5 1581.69    4995 1581.19  5014.3 1581.69
  5015.3 1583.68  5040.8 1584.19  5057.3 1586.89  5092.1 1594.29  5123.9 1603.12
  5128.1 1603.72  5166.4 1605.03    5179 1604.23  5244.5 1604.95  5312.5 1603.73
#Mann= 5 ,-1 , 0
  4369.5    .035       0  4486.8    .063       0  4505.7    .035       0
  4994.5    .035       0  5014.3    .035       0
#XS Ineff= 2 , 0
         4756.24 1604.35
Permanent Ineff=
       F       F
Bank Sta=4994.5,5014.3
XS Rating Curve= 0 ,0
Exp/Cntr=0.3,0.1

Type RM Length L Ch R = 1 ,3452    ,470,470,470
BEGIN DESCRIPTION:
Camping Meeting Creek 7.0
END DESCRIPTION:
XS GIS Cut Line= 4
      1926787.84     13918789.66        1927175.       13918425.
        1927275.       13918225.      1927313.39     13918118.26
#Sta/Elev= 30
  4463.5 1617.26  4478.6 1616.41  4544.3 1615.76  4594.4 1611.43  4644.9 1608.05
    4681 1607.44  4706.1 1602.55    4763 1602.26  4801.4 1595.32  4858.2  1592.3
  4882.9 1591.74  4936.5 1588.51  4985.9 1581.04  4994.2 1580.99  4995.2 1579.57
  4995.7 1579.07  5014.5 1579.07    5015 1579.57  5020.2 1581.05  5050.4 1584.08
  5100.7 1594.66  5122.5 1597.18  5125.8 1598.15  5132.5 1598.08  5139.8 1599.38
  5154.4 1600.51  5179.5 1600.66  5196.3 1602.92  5251.6  1603.5  5332.4 1603.05
#Mann= 4 ,-1 , 0
  4463.5    .063       0  4478.6    .035       0  4995.2    .035       0
    5015    .035       0
#XS Ineff= 2 , 0
                          5197.2         1605.43
Permanent Ineff=
       F       F
Bank Sta=4995.2,5015
XS Rating Curve= 0 ,0
Exp/Cntr=0.3,0.1

Type RM Length L Ch R = 1 ,2982    ,439,439,439
BEGIN DESCRIPTION:
Camping Meeting Creek 6.0
END DESCRIPTION:
XS GIS Cut Line= 4
      1927674.97     13918774.97        1927525.       13918625.
        1927375.       13918425.      1927356.31      13918209.5
#Sta/Elev= 30
  4783.9 1615.28  4787.6 1614.74  4801.7 1614.85    4816  1615.5  4869.8 1614.59
  4940.7 1601.95  4953.4    1597  4979.3 1585.21  4999.3 1581.94  5005.8 1579.91
    5010 1577.22  5010.7 1573.17  5011.2 1572.67  5030.6 1573.17  5030.8 1577.44
  5065.6 1584.94  5110.6 1587.48  5136.9 1592.21  5157.8 1594.01  5211.9 1596.27
    5235 1594.24  5260.8 1595.27  5275.8 1596.75  5290.9 1600.19  5342.6 1597.16
  5390.2 1598.66  5417.3 1598.24  5423.4 1600.11  5428.5 1600.52  5462.3 1600.46
#Mann= 6 ,-1 , 0
  4783.9    .063       0  4787.6    .094       0  4801.7    .063       0
  4979.3    .035       0  5010.7    .035       0  5030.6    .035       0
Bank Sta=5010.7,5030.6
XS Rating Curve= 0 ,0
Exp/Cntr=0.3,0.1

Type RM Length L Ch R = 1 ,2543    ,466,466,466
BEGIN DESCRIPTION:
Camping Meeting Creek 5.0
END DESCRIPTION:
XS GIS Cut Line= 3
      1927931.37     13918509.21      1927683.14     13918229.52
      1927514.23     13918020.62
#Sta/Elev= 30
  4652.5 1604.47  4664.2 1604.27  4681.5 1604.23    4686 1603.34  4720.6 1603.38
  4771.9 1605.36  4776.7 1604.72  4861.6 1603.63  4888.5 1601.23  4893.5 1600.98
  4914.7 1595.27  4931.7 1588.86  4953.2 1582.06  4985.3 1576.41  4985.5 1574.33
    4986 1573.83  5005.4 1574.33  5006.1 1575.38  5008.2 1576.37  5016.7 1577.92
  5029.3 1578.02  5054.1 1582.35  5072.6  1582.6  5091.7 1584.91  5110.8 1584.74
  5145.1  1587.8  5212.9 1589.52  5225.7 1590.58  5244.4 1594.37  5295.1 1599.23
#Mann= 6 ,-1 , 0
  4652.5    .063       0  4664.2    .094       0  4888.5    .035       0
  4985.5    .035       0  5005.4    .035       0  5054.1    .063       0
Bank Sta=4985.5,5005.4
XS Rating Curve= 0 ,0
Exp/Cntr=0.3,0.1

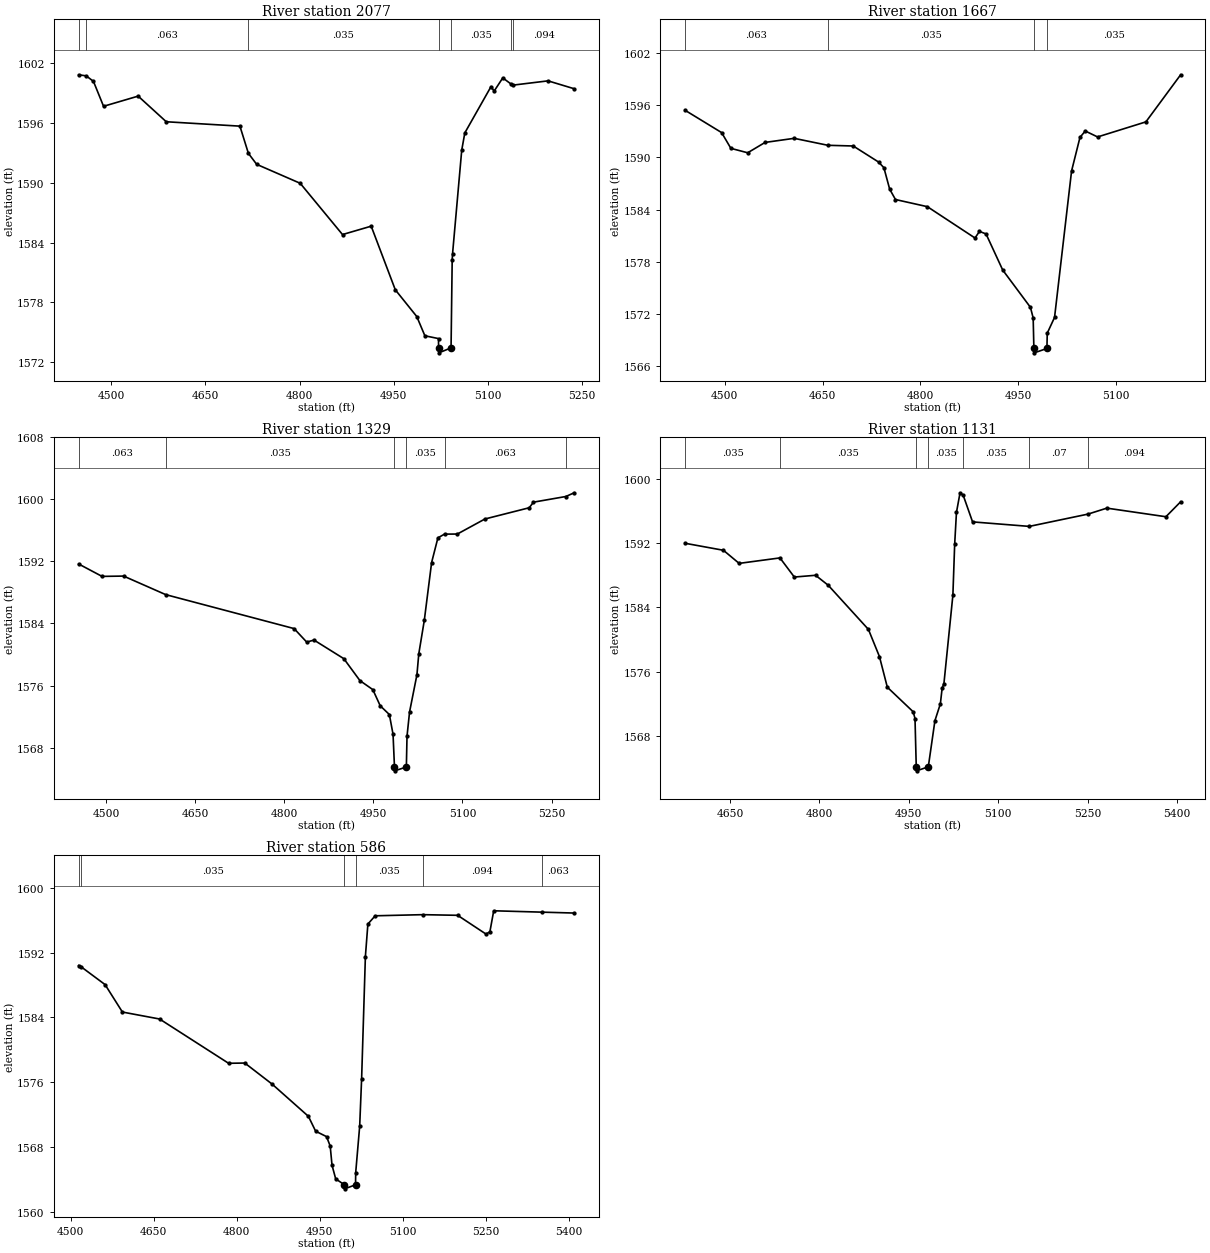
Type RM Length L Ch R = 1 ,2077    ,410,410,410
BEGIN DESCRIPTION:
Camping Meeting Creek 4.0
END DESCRIPTION:
XS GIS Cut Line= 3
      1928171.02     13918254.65        1927825.       13917825.
      1927595.21     13917764.41
#Sta/Elev= 30
  4448.1 1600.83  4460.2 1600.72  4471.7 1600.17  4487.8 1597.67  4542.9 1598.69
  4587.7 1596.12    4705 1595.68  4718.5 1592.95  4731.7 1591.85    4801 1589.95
  4868.4 1584.81  4914.1 1585.65  4952.5 1579.27  4986.7 1576.59  4999.6 1574.66
  5021.3 1574.38  5021.4 1573.45  5021.9 1572.95  5041.3 1573.45  5043.1 1582.26
  5043.6 1582.82  5058.3 1593.27  5063.2    1595    5105 1599.65  5109.9 1599.19
  5123.7 1600.52  5136.2 1599.93  5139.7 1599.79  5195.8 1600.22  5237.4 1599.43
#Mann= 7 ,-1 , 0
  4448.1    .035       0  4460.2    .063       0  4718.5    .035       0
  5021.4    .035       0  5041.3    .035       0  5136.2    .063       0
  5139.7    .094       0
Bank Sta=5021.4,5041.3
XS Rating Curve= 0 ,0
Exp/Cntr=0.3,0.1

Type RM Length L Ch R = 1 ,1667    ,338,338,338
BEGIN DESCRIPTION:
Camping Meeting Creek 3.0
END DESCRIPTION:
XS GIS Cut Line= 3
      1928334.66     13918021.31        1928075.       13917525.
        1928075.     13917325.04
#Sta/Elev= 30
  4439.2  1595.4  4495.2 1592.84  4509.4 1591.03  4535.2 1590.52  4561.9 1591.71
  4606.5 1592.18  4658.2 1591.38  4697.1  1591.3  4735.9 1589.46  4744.1 1588.81
    4753 1586.34  4761.9 1585.15  4810.8 1584.33  4883.9 1580.73  4890.7 1581.49
  4900.8  1581.2  4926.4 1577.05  4968.9 1572.77  4973.1 1571.55  4974.2 1568.04
  4974.7 1567.54  4994.2 1568.04  4994.7  1569.8  5005.9 1571.61    5032 1588.43
  5044.9 1592.29    5053 1593.02  5071.9 1592.34    5146 1594.07  5199.3 1599.48
#Mann= 4 ,-1 , 0
  4439.2    .063       0  4658.2    .035       0  4974.2    .035       0
  4994.2    .035       0
Bank Sta=4974.2,4994.2
XS Rating Curve= 0 ,0
Exp/Cntr=0.3,0.1

Type RM Length L Ch R = 1 ,1329    ,198,198,198
BEGIN DESCRIPTION:
Mapping XS ac235239
END DESCRIPTION:
XS GIS Cut Line= 3
      1928450.03     13917924.41      1928404.22     13917540.54
      1928295.81     13917106.57
#Sta/Elev= 30
  4454.1 1591.67  4493.5 1590.07  4529.8 1590.11  4600.6 1587.72  4816.7 1583.34
  4837.9  1581.6  4850.2 1581.86  4900.4 1579.46  4927.5 1576.63  4949.2 1575.47
  4961.6 1573.39    4977 1572.26  4983.2 1569.71  4985.6  1565.5  4986.1    1565
  5005.6  1565.5  5006.7 1569.46    5011  1572.6  5023.4 1577.39  5026.5 1580.08
  5035.8  1584.4  5048.1 1591.86  5058.7 1595.04  5069.8 1595.52  5091.4 1595.53
  5137.8 1597.47  5212.4 1598.92  5219.5 1599.64    5274 1600.37    5288 1600.85
#Mann= 6 ,-1 , 0
  4454.1    .063       0  4600.6    .035       0  4985.6    .035       0
  5005.6    .035       0  5069.8    .063       0    5274    .094       0
Bank Sta=4985.6,5005.6
XS Rating Curve= 0 ,0
Exp/Cntr=0.3,0.1

Type RM Length L Ch R = 1 ,1131    ,545,545,545
BEGIN DESCRIPTION:
Camping Meeting Creek 2.0
END DESCRIPTION:
XS GIS Cut Line= 3
      1928587.65     13917699.61        1928525.       13917275.
      1928515.84     13916873.61
#Sta/Elev= 30
  4574.9 1591.97  4639.1  1591.1  4665.5 1589.47  4733.9 1590.15    4758 1587.77
  4793.6 1587.99  4814.8 1586.75  4882.2 1581.26  4900.7 1577.88  4913.9 1574.07
  4957.3 1571.01  4960.3 1570.17  4962.4 1564.17  4962.9 1563.67  4982.6 1564.17
  4993.7 1569.91  5002.8    1572  5005.8 1573.95  5008.8 1574.53  5023.8 1585.51
  5026.8 1591.84  5029.8 1595.81  5035.8 1598.25  5041.1 1597.94  5056.8 1594.63
  5151.9 1594.07  5250.4  1595.6  5281.9 1596.34  5380.9 1595.27  5405.6 1597.13
#Mann= 7 ,-1 , 0
  4574.9    .035       0  4733.9    .035       0  4962.4    .035       0
  4982.6    .035       0  5041.1    .035       0  5151.9     .07       0
  5250.4    .094       0
Bank Sta=4962.4,4982.6
XS Rating Curve= 0 ,0
Exp/Cntr=0.3,0.1

Type RM Length L Ch R = 1 ,586     ,0,0,0
BEGIN DESCRIPTION:
Camping Meeting Creek 1.0
END DESCRIPTION:
XS GIS Cut Line= 3
      1928825.02     13917574.97        1929025.       13917125.
      1928825.01     13916775.02
#Sta/Elev= 30
  4514.1 1590.42    4518 1590.29  4561.9 1588.06  4593.2 1584.67  4660.4 1583.81
  4785.1 1578.34  4814.4 1578.37  4863.7 1575.77  4929.3 1571.79  4942.4 1569.95
  4962.1 1569.28  4968.7 1568.12    4972 1565.75  4978.6 1564.07  4994.3 1563.33
  4994.8 1562.83  5014.5 1563.33  5014.8 1564.84    5022 1570.58  5025.5 1576.45
  5032.3 1591.52  5036.8 1595.54    5050 1596.56  5135.9  1596.7    5199 1596.62
  5250.3  1594.3  5257.3 1594.59  5264.2 1597.18  5351.9 1597.01  5409.6  1596.9
#Mann= 6 ,-1 , 0
  4514.1    .035       0    4518    .035       0  4994.3    .035       0
  5014.5    .035       0  5135.9    .094       0  5351.9    .063       0
Bank Sta=4994.3,5014.5
XS Rating Curve= 0 ,0
Exp/Cntr=0.3,0.1

Chan Stop Cuts=-1
Use User Specified Reach Order=0
Composite Channel Slope=5