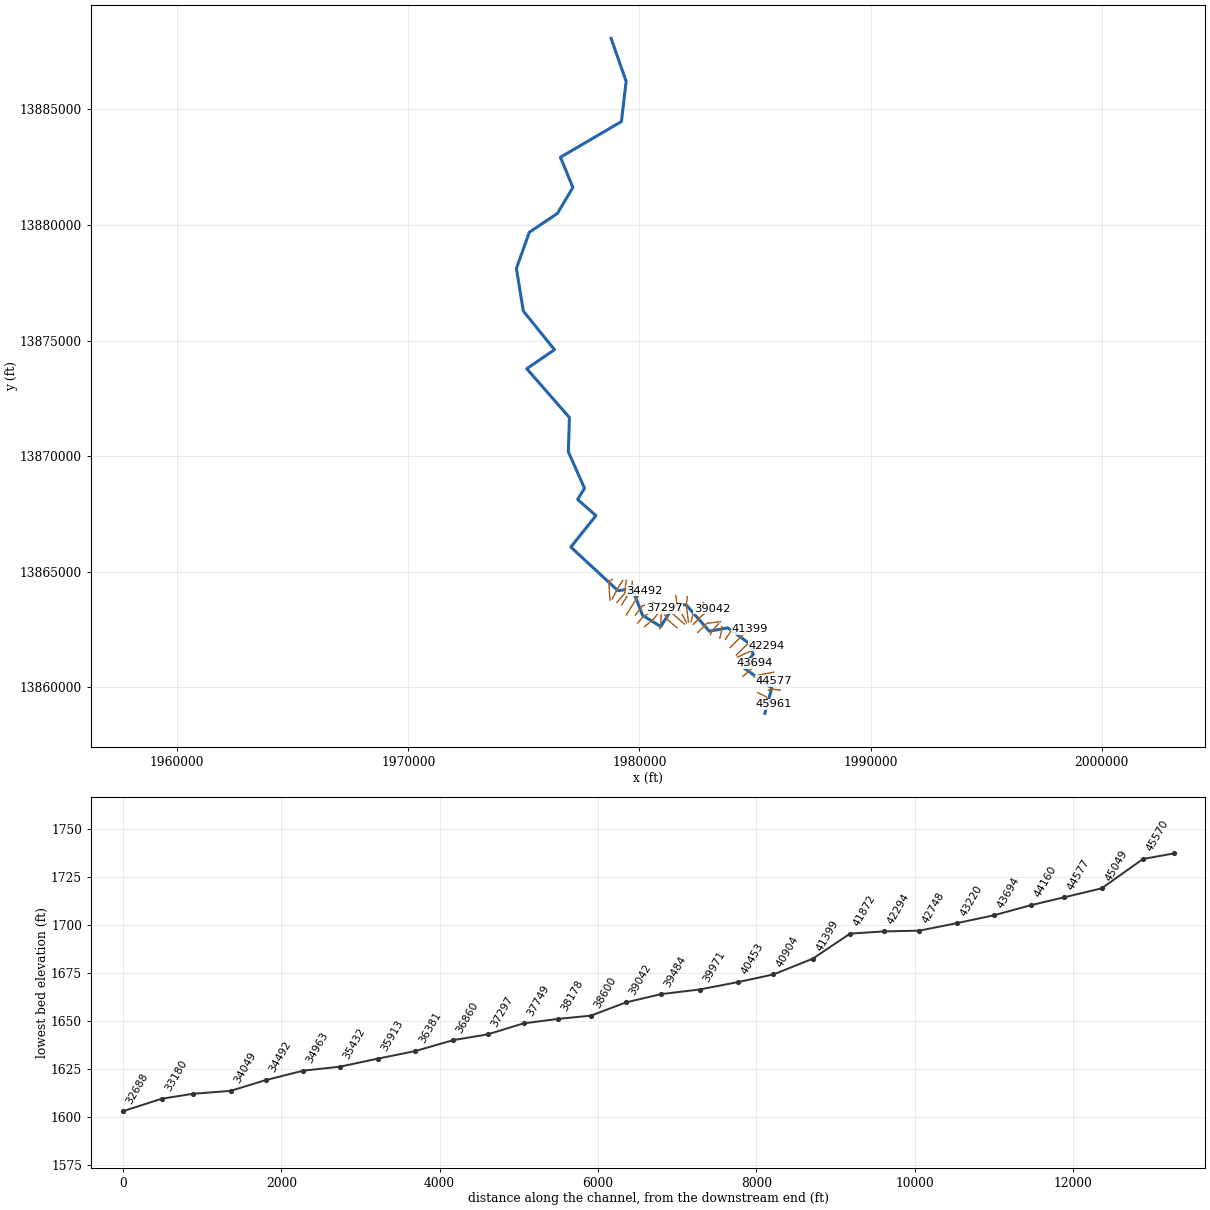
--- Cherry Creek.prj (project) ---

Proj Title=Cherry Creek Base Level Engineering
Current Plan=p01
Default Exp/Contr=0.3,0.1
English Units
Geom File=g01
Flow File=f01
Plan File=p01
BEGIN DESCRIPTION:
Cherry Creek
END DESCRIPTION:

--- Cherry Creek.p01 (plan) ---

Plan Title=Multiple Run
Short Identifier=Multiple
Geom File=g01
Flow File=f01
Subcritical Flow
K Sum by GR= 0
Std Step Tol= 0.01
Critical Tol= 0.01
Num of Std Step Trials= 20
Max Error Tol= 0.3
Flow Tol Ratio= 0.001
Split Flow NTrial= 30
Split Flow Tol= 0.02
Split Flow Ratio= 0.02
Log Output Level= 0
Friction Slope Method= 1
Unsteady Friction Slope Method= 2
Unsteady Bridges Friction Slope Method= 1
Parabolic Critical Depth
Global Vel Dist=  1 , 1 , 1
Global Log Level= 0
CheckData=True
Encroach Param= -1, 0, 0, 0
BEGIN DESCRIPTION:
Multiple Run
END DESCRIPTION:

--- Cherry Creek.f01 (steady flow) ---

Flow Title=Multiple
Number of Profiles=7
Profile Names=10-year,25-year,50-year,1pct_min,100-year,1pct_plu,500-year
River Rch & RM= Cherry Creek,Reach-1,45961
    1752    3080    4386    3023    6032   12036   11302
River Rch & RM= Cherry Creek,Reach-1,44160
    1817    3197    4557    3144    6272   12515   11769
River Rch & RM= Cherry Creek,Reach-1,43694
    2188    3874    5543    3835    7651   15266   14440
River Rch & RM= Cherry Creek,Reach-1,39042
    2403    4265    6114    4234    8448   16857   15987
River Rch & RM= Cherry Creek,Reach-1,36381
    2649    4720    6781    4705    9388   18731   17835
River Rch & RM= Cherry Creek,Reach-1,34049
    2720    4846    6962    4830    9638   19230   18303
River Rch & RM= Cherry Creek,Reach-1,31794
    3918    7095   10304    7219   14403   28738   27896
River Rch & RM= Cherry Creek,Reach-1,29981
    4004    7245   10516    7362   14690   29310   28411
River Rch & RM= Cherry Creek,Reach-1,26749
    4114    7442   10801    7558   15081   30091   29146
River Rch & RM= Cherry Creek,Reach-1,24439
    4613    8376   12185    8544   17048   34015   33078
River Rch & RM= Cherry Creek,Reach-1,20661
    6575   12104   17775   12572   25084   50048   49510
River Rch & RM= Cherry Creek,Reach-1,19511
    7378   13599   19988   14143   28219   56304   55741
River Rch & RM= Cherry Creek,Reach-1,13461
    7425   13650   20028   14143   28219   56304   55518
River Rch & RM= Cherry Creek,Reach-1,5077
    7721   14209   20863   14741   29412   58685   57936
River Rch & RM= Cherry Creek,Reach-1,4517
    8375   15440   22698   16054   32031   63910   63215
River Rch & RM= Cherry Creek,Reach-1,920
    8450   15578   22899   16195   32312   64472   63758
Boundary for River Rch & Prof#=Cherry Creek,Reach-1,1
Up Type=0
Dn Type=3
Dn Slope=0.005
Boundary for River Rch & Prof#=Cherry Creek,Reach-1,2
Up Type=0
Dn Type=3
Dn Slope=0.005
Boundary for River Rch & Prof#=Cherry Creek,Reach-1,3
Up Type=0
Dn Type=3
Dn Slope=0.005
Boundary for River Rch & Prof#=Cherry Creek,Reach-1,4
Up Type=0
Dn Type=3
Dn Slope=0.005
Boundary for River Rch & Prof#=Cherry Creek,Reach-1,5
Up Type=0
Dn Type=3
Dn Slope=0.005
Boundary for River Rch & Prof#=Cherry Creek,Reach-1,6
Up Type=0
Dn Type=3
Dn Slope=0.005
Boundary for River Rch & Prof#=Cherry Creek,Reach-1,7
Up Type=0
Dn Type=3
Dn Slope=0.005

--- Cherry Creek.g01 (geometry) ---

Geom Title=Existing Conditions

River Reach=Cherry Creek,Reach-1
Reach XY= 30
      1985425.00     13858875.00      1985722.94     13859969.15
      1984480.06     13860872.70      1984922.94     13861430.86
      1984738.27     13861911.37      1983819.03     13862572.86
      1983022.53     13862430.45      1982015.41     13863573.79
      1981511.68     13863561.63      1980922.56     13862630.39
      1980135.47     13863115.18      1979691.67     13864258.37
      1979068.95     13864183.16      1977033.16     13866068.95
      1978116.95     13867428.29      1977326.87     13868130.72
      1977624.62     13868609.73      1976926.20     13870184.59
      1976971.38     13871673.50      1975126.25     13873784.70
      1976325.07     13874606.71      1974978.83     13876276.58
      1974677.18     13878119.55      1975236.23     13879685.02
      1976452.14     13880501.16      1977121.18     13881626.59
      1976583.13     13882931.07      1979221.39     13884476.48
      1979424.32     13886211.08      1978775.00     13888075.00

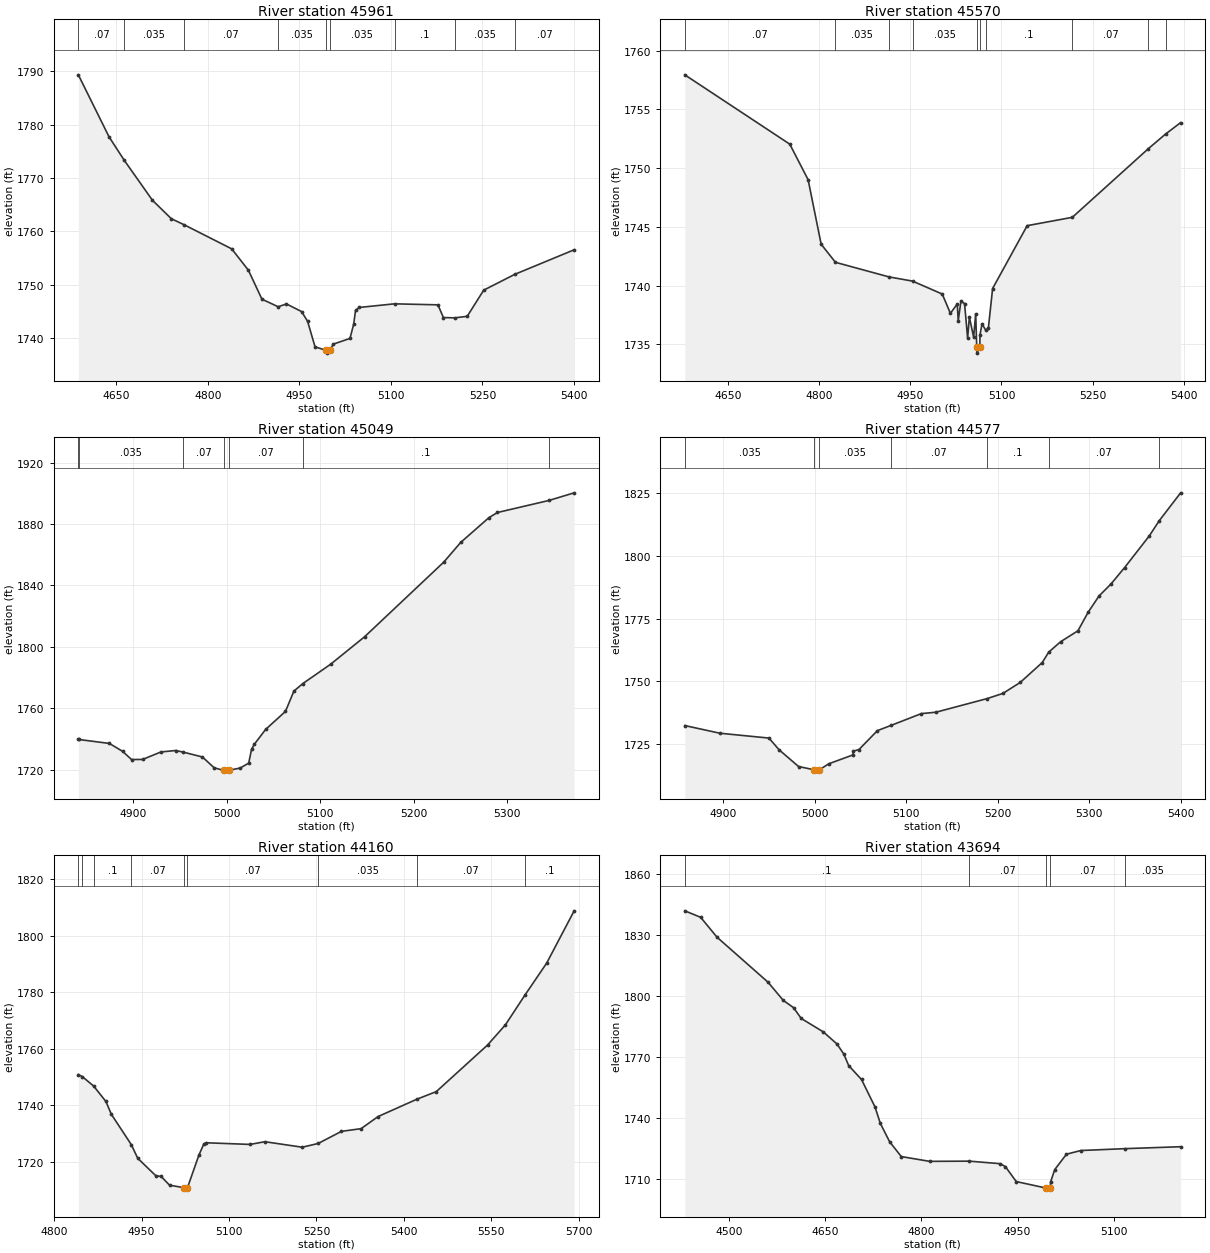
Type RM Length L Ch R = 1,45961,391,391,391
BEGIN DESCRIPTION:
Cherry Creek 87.0
END DESCRIPTION:
XS GIS Cut Line= 3
      1985025.01     13859175.00      1985425.00     13859275.00
      1985825.00     13859275.00
#Sta/Elev= 30
  4588.0 1789.33  4638.3 1777.71  4663.4 1773.28  4709.4 1765.82  4740.4 1762.36
  4761.5 1761.22  4839.3 1756.71  4866.6 1752.71  4888.8 1747.28  4915.4 1745.86
  4929.0 1746.39  4953.7 1744.96  4963.5 1743.16  4975.8 1738.35  4994.5 1737.67
  4994.9 1737.17  4999.6 1737.67  5006.0 1738.87  5033.0 1739.92  5039.1 1742.59
  5042.1 1745.16  5048.1 1745.73  5106.0 1746.41  5177.1 1746.22  5186.1 1743.84
  5204.6 1743.78  5225.1 1744.07  5252.1 1748.97  5303.1 1751.94  5400.3 1756.54
#Mann=9,-1,0
  4588.0    0.07       0  4663.4   0.035       0  4761.5    0.07       0
  4915.4   0.035       0  4994.5   0.035       0  4999.6   0.035       0
  5106.0     0.1       0  5204.6   0.035       0  5303.1    0.07       0
Bank Sta=4994.5,4999.6
Exp/Cntr=0.3,0.1

Type RM Length L Ch R = 1,45570,521,521,521
BEGIN DESCRIPTION:
Cherry Creek 86.0
END DESCRIPTION:
XS GIS Cut Line= 4
      1985119.58     13859770.45      1985471.59     13859598.96
      1985537.56     13859485.24      1985767.49     13859305.46
#Sta/Elev= 30
  4579.5 1757.94  4752.0 1752.04  4782.2 1749.01  4803.6 1743.52  4827.1 1741.98
  4915.0 1740.74  4953.8 1740.38  5002.6 1739.28  5016.0 1737.64  5027.3 1738.43
  5028.9 1737.01  5033.3 1738.66  5039.3 1738.47  5044.3 1735.53  5047.2 1737.31
  5054.2 1735.61  5057.6 1737.60  5059.3 1734.75  5059.7 1734.25  5064.4 1734.75
  5064.6 1735.78  5068.0 1736.74  5074.2 1736.19  5078.4 1736.37  5085.4 1739.75
  5142.2 1745.10  5216.4 1745.81  5341.5 1751.66  5369.9 1752.91  5394.4 1753.87
#Mann=10,-1,0
  4579.5    0.07       0  4827.1   0.035       0  4915.0    0.07       0
  4953.8   0.035       0  5059.3   0.035       0  5064.4   0.035       0
  5074.2     0.1       0  5216.4    0.07       0  5341.5   0.035       0
  5369.9    0.07       0
Bank Sta=5059.3,5064.4
Exp/Cntr=0.3,0.1

Type RM Length L Ch R = 1,45049,472,472,472
BEGIN DESCRIPTION:
Cherry Creek 85.0
END DESCRIPTION:
XS GIS Cut Line= 3
      1985574.96     13859874.99      1985725.00     13859925.00
      1986094.19     13859879.04
#Sta/Elev= 30
  4841.4 1739.64  4841.6 1739.64  4874.6 1737.04  4888.7 1731.90  4898.3 1726.55
  4910.1 1726.60  4929.8 1731.50  4945.6 1732.43  4953.6 1731.38  4974.1 1728.21
  4986.7 1721.14  4996.8 1719.49  4997.2 1718.99  5002.0 1719.49  5014.5 1721.00
  5023.6 1724.22  5026.6 1733.16  5029.6 1736.51  5041.7 1746.19  5062.9 1757.92
  5071.9 1771.16  5081.4 1776.04  5111.1 1788.64  5147.5 1806.58  5232.2 1855.26
  5250.3 1868.09  5280.5 1884.25  5289.6 1887.59  5344.6 1895.43  5371.6 1900.41
#Mann=7,-1,0
  4841.4    0.07       0  4841.6   0.035       0  4953.6    0.07       0
  4996.8    0.05       0  5002.0    0.07       0  5081.4     0.1       0
  5344.6    0.07       0
Bank Sta=4996.8,5002
Exp/Cntr=0.3,0.1

Type RM Length L Ch R = 1,44577,417,417,417
BEGIN DESCRIPTION:
Cherry Creek 84.0
END DESCRIPTION:
XS GIS Cut Line= 3
      1985324.99     13860174.99      1985425.00     13860275.00
      1985824.96     13860275.00
#Sta/Elev= 30
  4858.3 1732.47  4896.6 1729.42  4950.2 1727.49  4961.3 1722.82  4982.5 1716.19
  4999.9 1714.85  5000.4 1714.35  5005.2 1714.85  5015.5 1717.27  5041.6 1720.75
  5042.5 1722.30  5048.5 1722.94  5068.6 1730.45  5083.6 1732.54  5116.6 1737.22
  5132.5 1737.77  5188.3 1743.18  5205.6 1745.24  5224.6 1749.62  5248.6 1757.52
  5255.7 1761.67  5268.6 1765.78  5287.6 1770.16  5298.6 1777.44  5310.6 1783.99
  5323.6 1788.73  5338.6 1795.31  5365.6 1807.93  5376.3 1813.89  5399.7 1825.00
#Mann=7,-1,0
  4858.3   0.035       0  4999.9   0.035       0  5005.2   0.035       0
  5083.6    0.07       0  5188.3     0.1       0  5255.7    0.07       0
  5376.3     0.1       0
Bank Sta=4999.9,5005.2
Exp/Cntr=0.3,0.1

Type RM Length L Ch R = 1,44160,466,466,466
BEGIN DESCRIPTION:
Cherry Creek 83.0
END DESCRIPTION:
XS GIS Cut Line= 3
      1984974.99     13860475.00      1985125.00     13860525.00
      1985804.52     13860657.77
#Sta/Elev= 30
  4841.6 1750.83  4848.2 1750.14  4867.9 1746.76  4888.9 1741.31  4898.3 1736.75
  4932.5 1726.03  4943.5 1721.20  4974.3 1715.07  4983.7 1714.76  4998.1 1711.68
  5023.3 1710.79  5023.8 1710.29  5028.8 1710.79  5048.5 1722.38  5056.7 1726.19
  5060.7 1726.70  5136.0 1726.11  5161.6 1727.07  5225.7 1725.12  5252.9 1726.44
  5293.0 1730.74  5326.6 1731.69  5355.9 1735.99  5422.3 1742.11  5455.7 1744.81
  5543.6 1761.30  5574.2 1768.44  5607.9 1779.03  5644.9 1790.26  5692.1 1808.78
#Mann=9,-1,0
  4841.6   0.035       0  4848.2    0.07       0  4867.9     0.1       0
  4932.5    0.07       0  5023.3    0.05       0  5028.8    0.07       0
  5252.9   0.035       0  5422.3    0.07       0  5607.9     0.1       0
Bank Sta=5023.3,5028.8
Exp/Cntr=0.3,0.1

Type RM Length L Ch R = 1,43694,474,474,474
BEGIN DESCRIPTION:
Cherry Creek 82.0
END DESCRIPTION:
XS GIS Cut Line= 3
      1984474.97     13860474.97      1984848.21     13860800.62
      1984970.83     13861050.42
#Sta/Elev= 30
  4430.8 1841.91  4455.6 1838.71  4481.0 1828.96  4560.7 1806.80  4584.5 1797.84
  4600.5 1794.28  4612.4 1788.98  4646.9 1782.37  4668.2 1776.43  4678.8 1771.50
  4686.5 1765.79  4706.5 1758.96  4727.6 1745.43  4735.8 1737.43  4750.4 1728.32
  4768.6 1721.04  4812.8 1718.69  4874.8 1718.79  4923.0 1717.54  4931.1 1716.07
  4947.9 1708.76  4994.8 1705.53  4995.3 1705.03  5001.0 1705.53  5001.6 1708.64
  5008.0 1714.64  5026.3 1722.21  5048.7 1724.02  5117.8 1724.94  5204.4 1725.89
#Mann=5,-1,0
  4430.8     0.1       0  4874.8    0.07       0  4994.8    0.05       0
  5001.0    0.07       0  5117.8   0.035       0
Bank Sta=4994.8,5001
Exp/Cntr=0.3,0.1

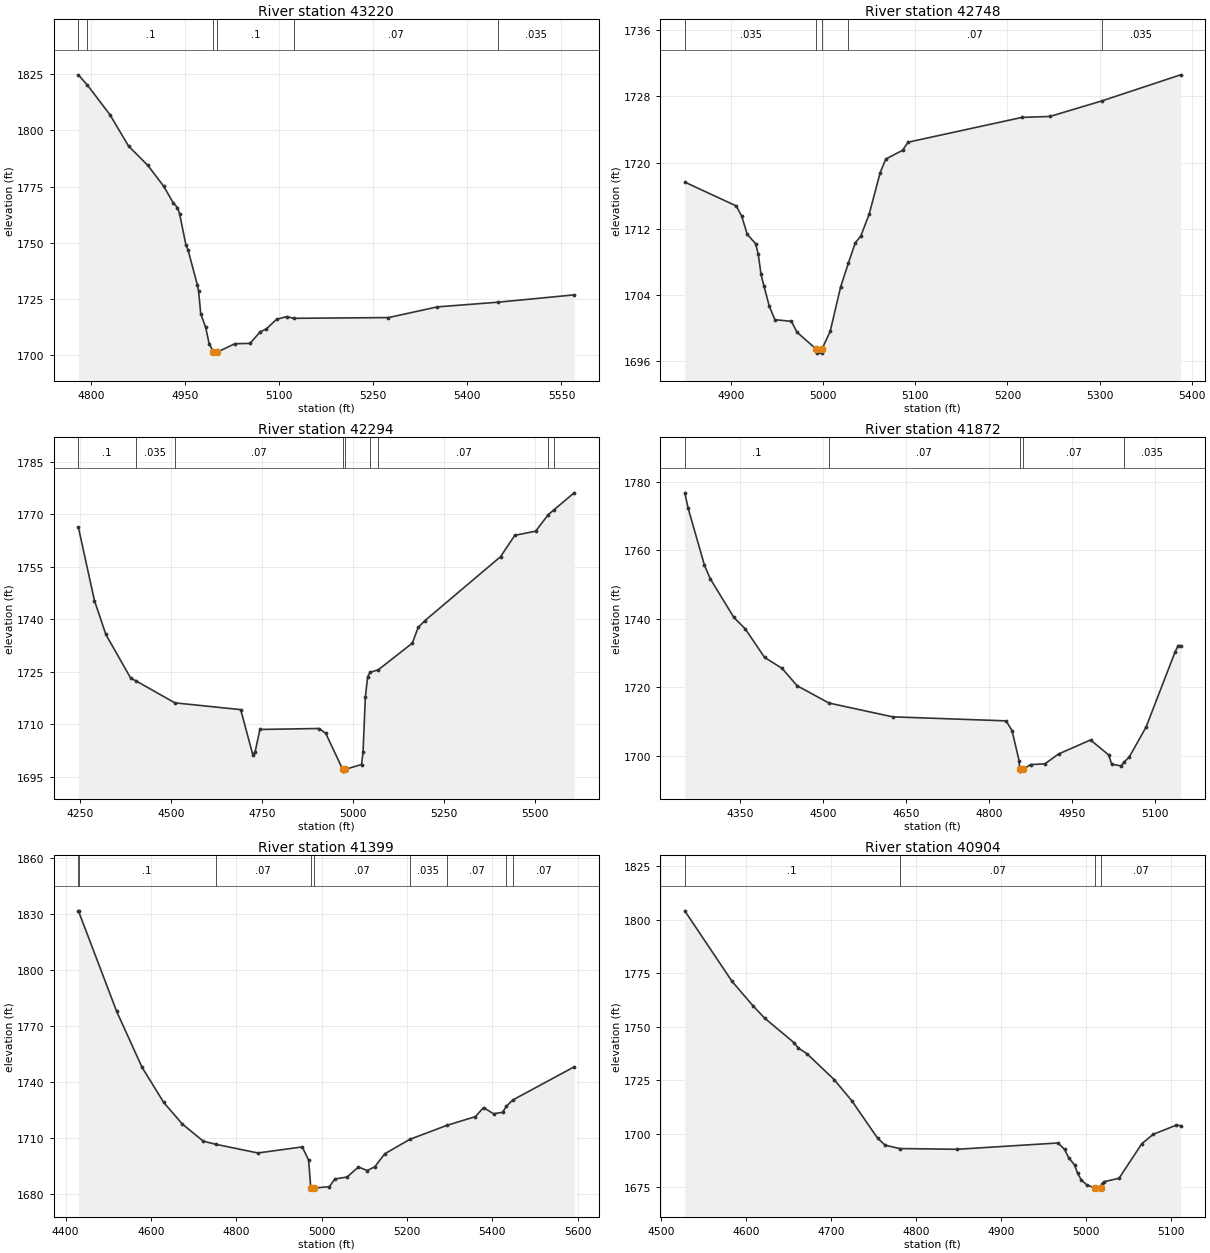
Type RM Length L Ch R = 1,43220,472,472,472
BEGIN DESCRIPTION:
Cherry Creek 81.0
END DESCRIPTION:
XS GIS Cut Line= 3
      1984282.09     13860973.48      1984475.00     13860875.00
      1985005.30     13861093.90
#Sta/Elev= 30
  4779.9 1824.70  4794.3 1820.15  4830.1 1807.04  4860.0 1792.98  4890.8 1784.37
  4916.0 1775.12  4931.2 1767.74  4937.9 1765.63  4941.3 1762.91  4951.4 1748.94
  4954.8 1746.77  4969.6 1731.24  4971.6 1728.60  4975.0 1718.40  4982.9 1712.30
  4988.4 1705.11  4995.3 1701.37  4995.8 1700.87  5001.7 1701.37  5029.3 1705.05
  5053.6 1705.21  5069.9 1710.38  5079.6 1711.64  5095.8 1715.90  5112.0 1717.12
  5123.0 1716.36  5274.3 1716.69  5352.2 1721.45  5448.8 1723.53  5570.2 1726.79
#Mann=6,-1,0
  4779.9    0.07       0  4794.3     0.1       0  4995.3    0.05       0
  5001.7     0.1       0  5123.0    0.07       0  5448.8   0.035       0
Bank Sta=4995.3,5001.7
Exp/Cntr=0.3,0.1

Type RM Length L Ch R = 1,42748,454,454,454
BEGIN DESCRIPTION:
Cherry Creek 80.0
END DESCRIPTION:
XS GIS Cut Line= 3
      1984624.98     13861225.00      1984775.00     13861225.00
      1985160.81     13861181.31
#Sta/Elev= 30
  4849.7 1717.65  4905.5 1714.78  4911.5 1713.54  4917.5 1711.34  4926.5 1710.23
  4929.5 1708.95  4932.5 1706.49  4935.6 1705.13  4941.5 1702.65  4947.5 1701.03
  4965.5 1700.83  4971.5 1699.52  4992.3 1697.49  4992.8 1696.99  4998.2 1696.99
  4998.7 1697.49  5007.6 1699.63  5018.9 1704.98  5027.4 1707.89  5034.8 1710.31
  5040.8 1711.13  5049.9 1713.78  5061.9 1718.81  5068.0 1720.44  5086.1 1721.49
  5092.1 1722.47  5215.9 1725.47  5246.1 1725.58  5302.8 1727.47  5388.0 1730.61
#Mann=5,-1,0
  4849.7   0.035       0  4992.3   0.035       0  4998.7   0.035       0
  5027.4    0.07       0  5302.8   0.035       0
Bank Sta=4992.3,4998.7
Exp/Cntr=0.3,0.1

Type RM Length L Ch R = 1,42294,422,422,422
BEGIN DESCRIPTION:
Cherry Creek 79.0
END DESCRIPTION:
XS GIS Cut Line= 3
      1984237.21     13861306.98      1984925.00     13861625.00
      1985500.35     13861806.99
#Sta/Elev= 30
  4246.3 1766.31  4290.5 1745.32  4321.9 1735.61  4390.0 1723.16  4404.3 1722.38
  4511.3 1716.08  4692.1 1714.14  4725.1 1701.31  4731.7 1702.14  4744.9 1708.48
  4906.9 1708.75  4925.6 1707.37  4972.1 1697.07  4972.6 1696.57  4978.5 1697.07
  5023.9 1698.46  5028.0 1702.02  5034.3 1717.72  5040.6 1723.55  5047.1 1724.78
  5070.2 1725.55  5163.3 1733.15  5179.3 1737.63  5197.9 1739.58  5405.6 1757.86
  5444.6 1763.95  5502.0 1765.14  5536.4 1769.85  5552.1 1771.23  5607.5 1776.09
#Mann=9,-1,0
  4246.3     0.1       0  4404.3   0.035       0  4511.3    0.07       0
  4972.1    0.05       0  4978.5    0.07       0  5047.1     0.1       0
  5070.2    0.07       0  5536.4   0.035       0  5552.1    0.07       0
Bank Sta=4972.1,4978.5
Exp/Cntr=0.3,0.1

Type RM Length L Ch R = 1,41872,473,473,473
BEGIN DESCRIPTION:
Cherry Creek 78.0
END DESCRIPTION:
XS GIS Cut Line= 3
      1984189.12     13861393.44      1984725.00     13861925.00
      1984824.98     13862024.98
#Sta/Elev= 30
  4250.0 1776.83  4255.9 1772.43  4285.6 1755.64  4296.1 1751.69  4338.6 1740.42
  4359.4 1737.03  4394.3 1728.69  4425.6 1725.53  4453.2 1720.40  4510.7 1715.35
  4625.7 1711.32  4830.8 1710.14  4841.6 1707.27  4854.4 1698.42  4855.1 1695.94
  4855.6 1695.44  4861.7 1695.94  4875.0 1697.36  4900.8 1697.56  4925.7 1700.46
  4983.5 1704.55  5016.2 1700.18  5021.7 1697.46  5038.7 1696.97  5044.2 1698.13
  5053.5 1699.58  5084.1 1708.42  5136.2 1730.28  5141.7 1732.14  5146.2 1732.16
#Mann=5,-1,0
  4250.0     0.1       0  4510.7    0.07       0  4855.1    0.05       0
  4861.7    0.07       0  5044.2   0.035       0
Bank Sta=4855.1,4861.7
Exp/Cntr=0.3,0.1

Type RM Length L Ch R = 1,41399,495,495,495
BEGIN DESCRIPTION:
Cherry Creek 77.0
END DESCRIPTION:
XS GIS Cut Line= 3
      1983924.97     13861724.97      1984325.00     13862125.00
      1984764.48     13862527.25
#Sta/Elev= 30
  4429.9 1831.51  4430.3 1831.36  4519.7 1777.60  4579.1 1747.68  4630.0 1728.78
  4673.3 1717.30  4722.4 1708.08  4751.5 1706.40  4850.6 1701.73  4954.5 1704.98
  4969.4 1697.87  4974.5 1682.85  4975.0 1682.35  4981.2 1682.85  5018.2 1683.71
  5030.9 1687.83  5059.1 1688.80  5086.1 1694.21  5106.8 1692.30  5124.6 1694.37
  5147.7 1701.29  5206.3 1709.02  5292.6 1716.47  5360.0 1721.21  5379.2 1726.05
  5402.5 1722.74  5423.8 1723.52  5432.7 1726.79  5447.6 1730.11  5591.4 1747.89
#Mann=9,-1,0
  4429.9    0.07       0  4430.3     0.1       0  4751.5    0.07       0
  4974.5    0.05       0  4981.2    0.07       0  5206.3   0.035       0
  5292.6    0.07       0  5432.7   0.035       0  5447.6    0.07       0
Bank Sta=4974.5,4981.2
Exp/Cntr=0.3,0.1

Type RM Length L Ch R = 1,40904,451,451,451
BEGIN DESCRIPTION:
Cherry Creek 76.0
END DESCRIPTION:
XS GIS Cut Line= 3
      1983725.02     13862075.03      1983975.00     13862475.00
      1984025.01     13862575.03
#Sta/Elev= 30
  4528.1 1804.08  4583.6 1771.23  4608.3 1759.80  4622.3 1753.93  4657.2 1742.37
  4661.4 1740.16  4672.0 1737.36  4703.9 1725.32  4724.7 1715.42  4755.1 1697.92
  4764.0 1694.68  4781.0 1693.13  4848.7 1692.78  4967.4 1695.74  4975.0 1692.73
  4979.8 1688.95  4986.9 1685.43  4990.4 1681.61  4994.6 1678.59  5001.2 1676.15
  5011.2 1674.69  5011.7 1674.19  5018.0 1674.69  5019.1 1676.76  5021.1 1677.60
  5039.2 1679.27  5066.0 1695.40  5079.4 1699.78  5106.3 1704.00  5111.6 1703.81
#Mann=4,-1,0
  4528.1     0.1       0  4781.0    0.07       0  5011.2    0.05       0
  5018.0    0.07       0
Bank Sta=5011.2,5018
Exp/Cntr=0.3,0.1

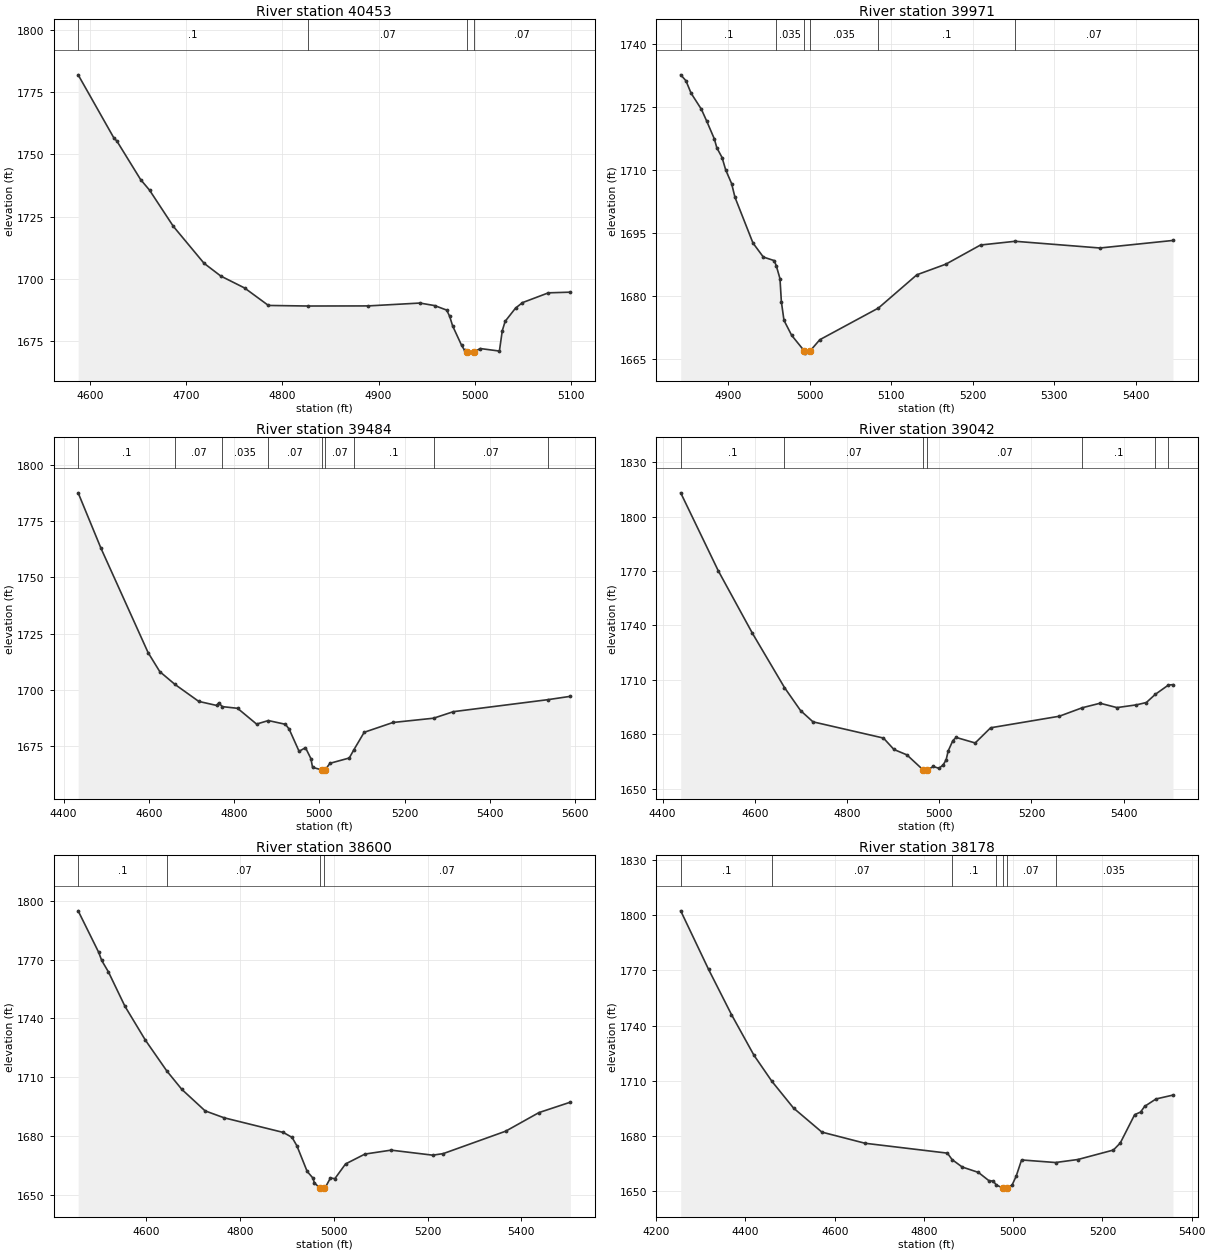
Type RM Length L Ch R = 1,40453,482,482,482
BEGIN DESCRIPTION:
Cherry Creek 75.0
END DESCRIPTION:
XS GIS Cut Line= 3
      1983475.01     13862125.02      1983575.00     13862525.00
      1983575.00     13862625.01
#Sta/Elev= 30
  4587.4 1781.84  4624.6 1756.50  4627.7 1755.27  4652.4 1739.82  4661.7 1735.57
  4686.4 1721.08  4718.4 1706.24  4735.9 1701.10  4760.6 1696.33  4785.4 1689.32
  4826.3 1689.09  4889.1 1689.13  4943.1 1690.28  4958.4 1689.26  4970.9 1687.46
  4974.0 1684.99  4977.1 1681.13  4986.4 1673.35  4989.5 1671.37  4992.5 1670.69
  4993.0 1670.19  4999.4 1670.69  5005.9 1672.03  5025.8 1671.02  5028.8 1679.19
  5031.8 1682.96  5042.6 1688.25  5049.8 1690.45  5076.8 1694.38  5099.7 1694.65
#Mann=4,-1,0
  4587.4     0.1       0  4826.3    0.07       0  4992.5    0.05       0
  4999.4    0.07       0
Bank Sta=4992.5,4999.4
Exp/Cntr=0.3,0.1

Type RM Length L Ch R = 1,39971,487,487,487
BEGIN DESCRIPTION:
Cherry Creek 74.0
END DESCRIPTION:
XS GIS Cut Line= 3
      1983075.00     13862275.01      1983125.00     13862425.00
      1983428.65     13862750.70
#Sta/Elev= 30
  4842.0 1732.74  4848.4 1731.34  4854.7 1728.37  4867.4 1724.51  4873.7 1721.78
  4883.2 1717.47  4886.3 1715.32  4892.7 1713.01  4897.2 1710.03  4904.4 1706.80
  4908.5 1703.54  4930.6 1692.61  4943.3 1689.27  4956.5 1688.43  4959.1 1687.24
  4963.7 1684.11  4965.4 1678.62  4968.6 1674.17  4978.0 1670.60  4993.6 1666.85
  4994.1 1666.35  5000.5 1666.85  5012.5 1669.55  5084.4 1677.11  5131.5 1685.04
  5167.0 1687.57  5209.5 1692.14  5251.9 1693.03  5355.9 1691.43  5445.4 1693.23
#Mann=6,-1,0
  4842.0     0.1       0  4959.1   0.035       0  4993.6   0.035       0
  5000.5   0.035       0  5084.4     0.1       0  5251.9    0.07       0
Bank Sta=4993.6,5000.5
Exp/Cntr=0.3,0.1

Type RM Length L Ch R = 1,39484,442,442,442
BEGIN DESCRIPTION:
Cherry Creek 73.0
END DESCRIPTION:
XS GIS Cut Line= 3
      1982525.02     13862375.02      1982925.00     13862775.00
      1983510.60     13862837.74
#Sta/Elev= 30
  4434.3 1787.61  4487.9 1762.94  4598.4 1716.59  4625.8 1708.15  4661.6 1702.44
  4717.2 1694.92  4759.3 1693.12  4763.9 1694.24  4772.6 1692.60  4808.2 1691.86
  4852.8 1684.85  4880.4 1686.41  4920.5 1684.75  4929.2 1682.61  4952.5 1672.74
  4967.5 1674.37  4980.1 1669.54  4984.1 1665.64  5006.3 1664.44  5006.8 1663.94
  5013.4 1664.44  5024.9 1667.42  5070.2 1669.77  5080.7 1673.33  5105.2 1681.20
  5172.8 1685.56  5268.0 1687.46  5314.6 1690.37  5535.4 1695.68  5588.9 1697.18
#Mann=9,-1,0
  4434.3     0.1       0  4661.6    0.07       0  4772.6   0.035       0
  4880.4    0.07       0  5006.3    0.05       0  5013.4    0.07       0
  5080.7     0.1       0  5268.0    0.07       0  5535.4   0.035       0
Bank Sta=5006.3,5013.4
Exp/Cntr=0.3,0.1

Type RM Length L Ch R = 1,39042,442,442,442
BEGIN DESCRIPTION:
Cherry Creek 72.0
END DESCRIPTION:
XS GIS Cut Line= 3
      1982324.99     13862724.99      1982725.00     13863125.00
      1983148.25     13863395.12
#Sta/Elev= 30
  4439.1 1813.13  4520.4 1770.23  4594.6 1735.70  4664.2 1705.74  4699.1 1693.04
  4726.1 1686.82  4878.9 1677.88  4901.7 1671.58  4929.8 1668.60  4965.7 1660.14
  4966.2 1659.64  4973.1 1660.14  4987.0 1662.20  4999.2 1661.20  5008.3 1663.05
  5014.9 1665.85  5019.2 1670.71  5029.5 1676.49  5036.5 1678.23  5077.9 1675.17
  5111.4 1683.55  5260.3 1689.91  5310.4 1694.62  5348.8 1697.08  5385.4 1694.68
  5427.6 1696.19  5449.2 1697.49  5468.5 1701.97  5497.0 1707.12  5506.9 1707.34
#Mann=7,-1,0
  4439.1     0.1       0  4664.2    0.07       0  4965.7    0.05       0
  4973.1    0.07       0  5310.4     0.1       0  5468.5    0.07       0
  5497.0     0.1       0
Bank Sta=4965.7,4973.1
Exp/Cntr=0.3,0.1

Type RM Length L Ch R = 1,38600,422,422,422
BEGIN DESCRIPTION:
Cherry Creek 71.0
END DESCRIPTION:
XS GIS Cut Line= 3
      1982232.03     13862844.72      1982375.00     13863375.00
      1982778.53     13863670.72
#Sta/Elev= 30
  4455.0 1794.87  4498.9 1773.61  4505.1 1769.59  4519.6 1763.65  4554.8 1746.11
  4598.3 1728.85  4643.9 1713.14  4676.0 1703.70  4725.7 1692.72  4766.1 1689.19
  4892.5 1681.70  4911.1 1679.16  4921.4 1674.86  4943.2 1661.82  4955.2 1658.51
  4958.7 1655.96  4970.4 1653.26  4970.9 1652.76  4978.2 1653.26  4982.1 1653.69
  4992.9 1658.48  5002.2 1658.08  5025.1 1665.62  5066.4 1670.66  5122.2 1672.67
  5211.0 1670.10  5233.4 1670.90  5366.4 1682.34  5437.4 1691.84  5504.5 1697.17
#Mann=4,-1,0
  4455.0     0.1       0  4643.9    0.07       0  4970.4    0.05       0
  4978.2    0.07       0
Bank Sta=4970.4,4978.2
Exp/Cntr=0.3,0.1

Type RM Length L Ch R = 1,38178,429,429,429
BEGIN DESCRIPTION:
Cherry Creek 70.0
END DESCRIPTION:
XS GIS Cut Line= 3
      1982119.41     13862831.18      1982025.00     13863575.00
      1982074.99     13863924.96
#Sta/Elev= 30
  4254.8 1802.47  4317.2 1770.64  4368.6 1746.01  4419.1 1723.84  4459.2 1709.69
  4507.7 1695.13  4571.2 1682.05  4668.0 1675.98  4852.5 1670.61  4863.2 1667.06
  4885.7 1663.06  4922.0 1660.12  4945.6 1655.62  4955.3 1655.39  4962.0 1653.32
  4977.5 1651.52  4978.0 1651.02  4985.6 1651.52  4997.5 1653.22  5006.7 1658.07
  5018.8 1666.90  5095.0 1665.50  5145.0 1667.14  5224.6 1672.29  5240.0 1676.12
  5272.3 1691.56  5285.5 1692.95  5294.6 1696.05  5320.0 1700.08  5358.1 1702.20
#Mann=7,-1,0
  4254.8     0.1       0  4459.2    0.07       0  4863.2     0.1       0
  4962.0    0.07       0  4977.5    0.05       0  4985.6    0.07       0
  5095.0   0.035       0
Bank Sta=4977.5,4985.6
Exp/Cntr=0.3,0.1

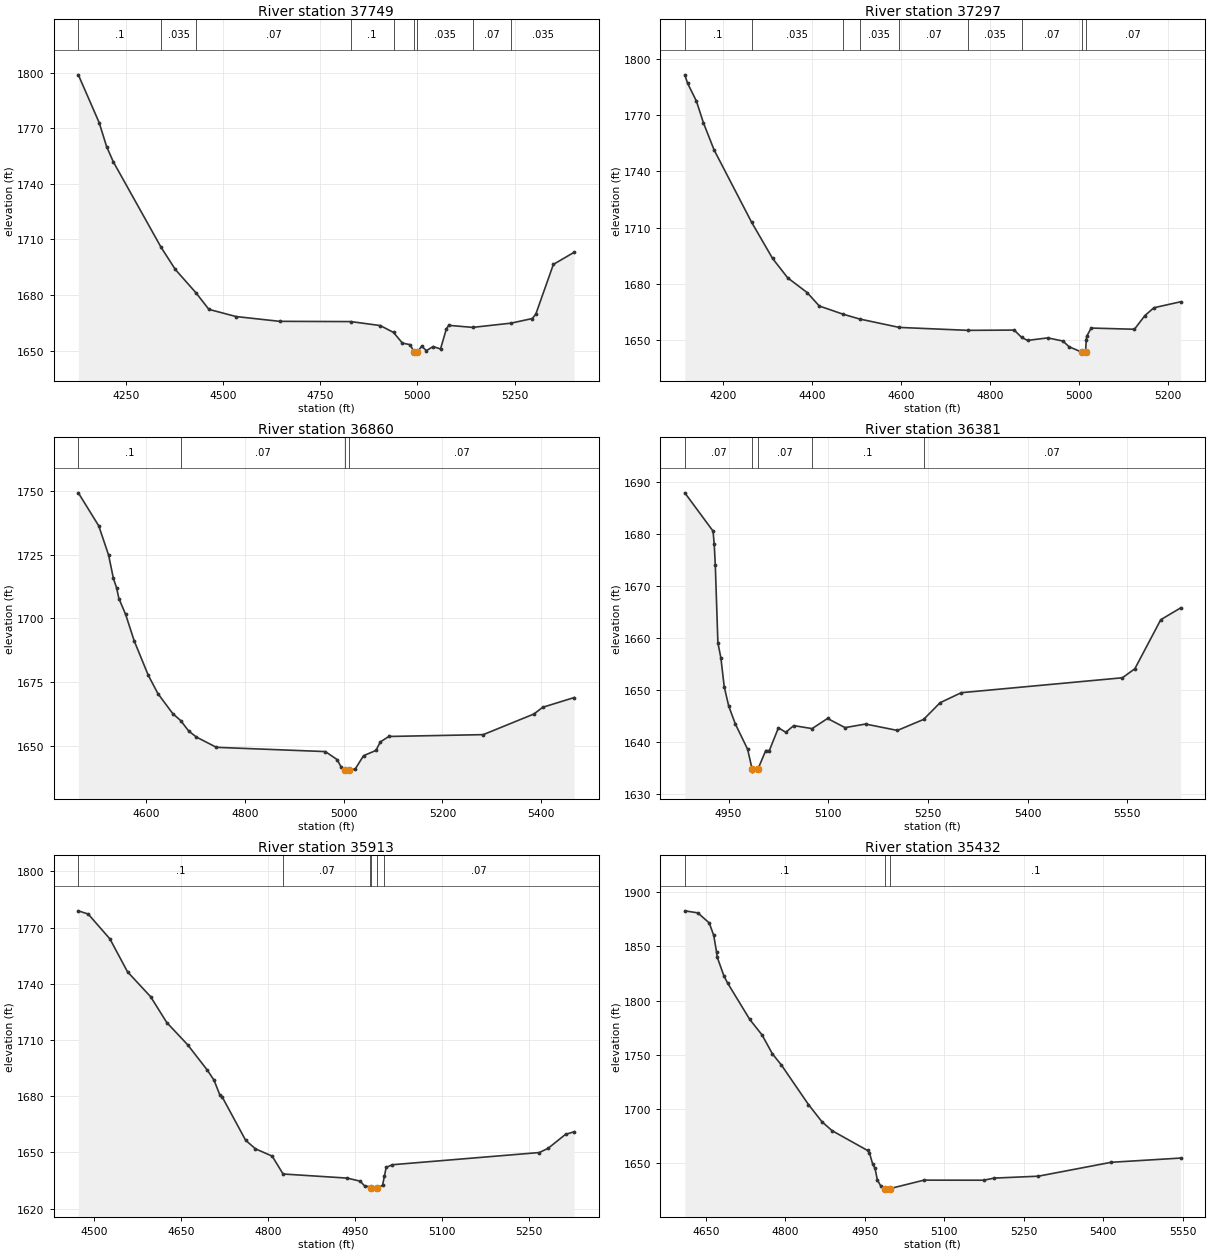
Type RM Length L Ch R = 1,37749,452,452,452
BEGIN DESCRIPTION:
Cherry Creek 69.0
END DESCRIPTION:
XS GIS Cut Line= 3
      1982032.86     13862804.75      1981625.00     13863575.00
      1981575.00     13863975.01
#Sta/Elev= 30
  4128.4 1798.77  4181.9 1773.03  4201.1 1760.11  4218.2 1751.92  4341.0 1705.83
  4377.7 1693.85  4431.0 1681.21  4464.0 1672.33  4533.9 1668.45  4645.9 1665.87
  4829.2 1665.73  4904.7 1663.59  4938.7 1659.88  4961.6 1654.13  4981.9 1653.28
  4991.4 1649.23  4991.9 1648.73  4999.6 1649.23  5011.1 1652.49  5023.2 1650.07
  5040.5 1652.29  5059.5 1650.96  5074.6 1661.82  5080.7 1663.71  5142.2 1662.61
  5241.0 1664.90  5295.3 1667.37  5304.4 1669.69  5349.7 1696.58  5403.1 1703.10
#Mann=9,-1,0
  4128.4     0.1       0  4341.0   0.035       0  4431.0    0.07       0
  4829.2     0.1       0  4938.7   0.035       0  4991.4   0.035       0
  4999.6   0.035       0  5142.2    0.07       0  5241.0   0.035       0
Bank Sta=4991.4,4999.6
Exp/Cntr=0.3,0.1

Type RM Length L Ch R = 1,37297,437,437,437
BEGIN DESCRIPTION:
Cherry Creek 68.0
END DESCRIPTION:
XS GIS Cut Line= 3
      1981946.50     13862739.34      1981275.00     13863325.00
      1981075.02     13863424.99
#Sta/Elev= 30
  4113.6 1791.49  4119.8 1787.03  4139.7 1777.47  4155.6 1765.81  4179.5 1751.40
  4263.6 1712.93  4310.9 1693.54  4344.9 1683.19  4388.6 1675.34  4415.9 1668.17
  4469.4 1663.79  4506.5 1661.23  4595.7 1656.74  4750.4 1655.17  4854.1 1655.32
  4870.9 1651.38  4884.1 1649.81  4929.7 1651.15  4963.6 1649.47  4977.3 1646.45
  5006.3 1643.52  5006.8 1643.02  5014.5 1643.52  5016.0 1649.86  5017.1 1652.05
  5027.2 1656.40  5124.4 1655.75  5147.9 1663.06  5168.1 1667.23  5228.2 1670.42
#Mann=9,-1,0
  4113.6     0.1       0  4263.6   0.035       0  4469.4    0.07       0
  4506.5   0.035       0  4595.7    0.07       0  4750.4   0.035       0
  4870.9    0.07       0  5006.3    0.05       0  5014.5    0.07       0
Bank Sta=5006.3,5014.5
Exp/Cntr=0.3,0.1

Type RM Length L Ch R = 1,36860,479,479,479
BEGIN DESCRIPTION:
Cherry Creek 67.0
END DESCRIPTION:
XS GIS Cut Line= 3
      1981624.97     13862575.03      1981225.00     13862925.00
      1980974.98     13863325.03
#Sta/Elev= 30
  4463.3 1749.36  4504.7 1736.34  4524.6 1724.85  4534.3 1715.70  4540.6 1712.11
  4545.4 1707.82  4559.0 1701.59  4576.4 1691.16  4604.6 1677.76  4624.3 1670.47
  4654.7 1662.52  4670.3 1659.89  4686.6 1655.76  4702.3 1653.38  4742.7 1649.35
  4963.1 1647.68  4987.0 1644.53  4995.1 1641.56  5002.3 1640.50  5002.8 1640.00
  5010.6 1640.50  5023.4 1640.80  5040.4 1646.07  5065.3 1648.12  5074.4 1651.48
  5091.5 1653.62  5282.6 1654.34  5385.2 1662.46  5402.9 1665.09  5466.5 1668.91
#Mann=4,-1,0
  4463.3     0.1       0  4670.3    0.07       0  5002.3    0.05       0
  5010.6    0.07       0
Bank Sta=5002.3,5010.6
Exp/Cntr=0.3,0.1

Type RM Length L Ch R = 1,36381,468,468,468
BEGIN DESCRIPTION:
Cherry Creek 66.0
END DESCRIPTION:
XS GIS Cut Line= 3
      1980875.01     13862525.03      1980925.00     13862625.00
      1980942.90     13863258.98
#Sta/Elev= 30
  4884.1 1687.86  4926.6 1680.50  4928.4 1677.92  4930.0 1673.94  4933.9 1659.02
  4938.4 1656.09  4943.4 1650.58  4950.1 1646.86  4960.2 1643.38  4978.6 1638.53
  4985.2 1634.82  4985.7 1634.32  4994.5 1634.82  5005.9 1638.28  5011.3 1638.28
  5025.0 1642.66  5036.0 1641.79  5048.0 1643.08  5075.6 1642.50  5098.9 1644.45
  5125.2 1642.69  5156.0 1643.38  5204.0 1642.15  5243.4 1644.27  5268.2 1647.48
  5300.1 1649.41  5542.5 1652.28  5561.2 1654.01  5600.2 1663.45  5630.1 1665.72
#Mann=5,-1,0
  4884.1    0.07       0  4985.2    0.05       0  4994.5    0.07       0
  5075.6     0.1       0  5243.4    0.07       0
Bank Sta=4985.2,4994.5
Exp/Cntr=0.3,0.1

Type RM Length L Ch R = 1,35913,481,481,481
BEGIN DESCRIPTION:
Cherry Creek 65.0
END DESCRIPTION:
XS GIS Cut Line= 3
      1980224.99     13862624.99      1980625.00     13862975.00
      1980826.06     13863228.15
#Sta/Elev= 30
  4472.9 1779.00  4489.9 1777.28  4527.4 1763.99  4557.7 1746.44  4597.5 1733.16
  4625.5 1719.31  4661.3 1707.52  4695.4 1693.91  4706.9 1688.56  4716.6 1680.88
  4720.9 1679.65  4761.3 1656.52  4778.3 1651.93  4807.1 1648.04  4825.9 1638.50
  4936.4 1636.31  4959.0 1634.66  4966.6 1632.05  4975.4 1631.75  4977.7 1630.92
  4978.2 1630.42  4987.1 1630.92  4997.3 1632.43  5000.6 1637.37  5003.6 1642.02
  5014.3 1643.45  5267.6 1649.95  5282.9 1652.23  5312.8 1659.66  5327.7 1661.03
#Mann=6,-1,0
  4472.9     0.1       0  4825.9    0.07       0  4975.4     0.1       0
  4977.7    0.05       0  4987.1     0.1       0  5000.6    0.07       0
Bank Sta=4977.7,4987.1
Exp/Cntr=0.3,0.1

Type RM Length L Ch R = 1,35432,469,469,469
BEGIN DESCRIPTION:
Cherry Creek 64.0
END DESCRIPTION:
XS GIS Cut Line= 3
      1979925.01     13862775.01      1980175.00     13863075.00
      1980656.52     13863331.33
#Sta/Elev= 30
  4610.0 1882.81  4634.7 1880.91  4656.1 1871.65  4664.6 1860.20  4670.0 1844.72
  4671.0 1840.37  4683.8 1822.88  4690.9 1816.14  4732.7 1782.62  4755.9 1768.33
  4775.4 1750.94  4792.4 1740.60  4843.5 1704.18  4869.1 1688.24  4888.2 1680.06
  4955.0 1661.85  4958.5 1659.70  4964.9 1648.98  4969.2 1645.29  4973.4 1634.80
  4979.8 1629.23  4987.9 1626.71  4988.4 1626.21  4997.4 1626.71  5061.5 1634.50
  5174.2 1634.43  5194.0 1636.37  5277.3 1638.14  5414.9 1650.95  5546.0 1654.85
#Mann=3,-1,0
  4610.0     0.1       0  4987.9    0.05       0  4997.4     0.1       0
Bank Sta=4987.9,4997.4
Exp/Cntr=0.3,0.1

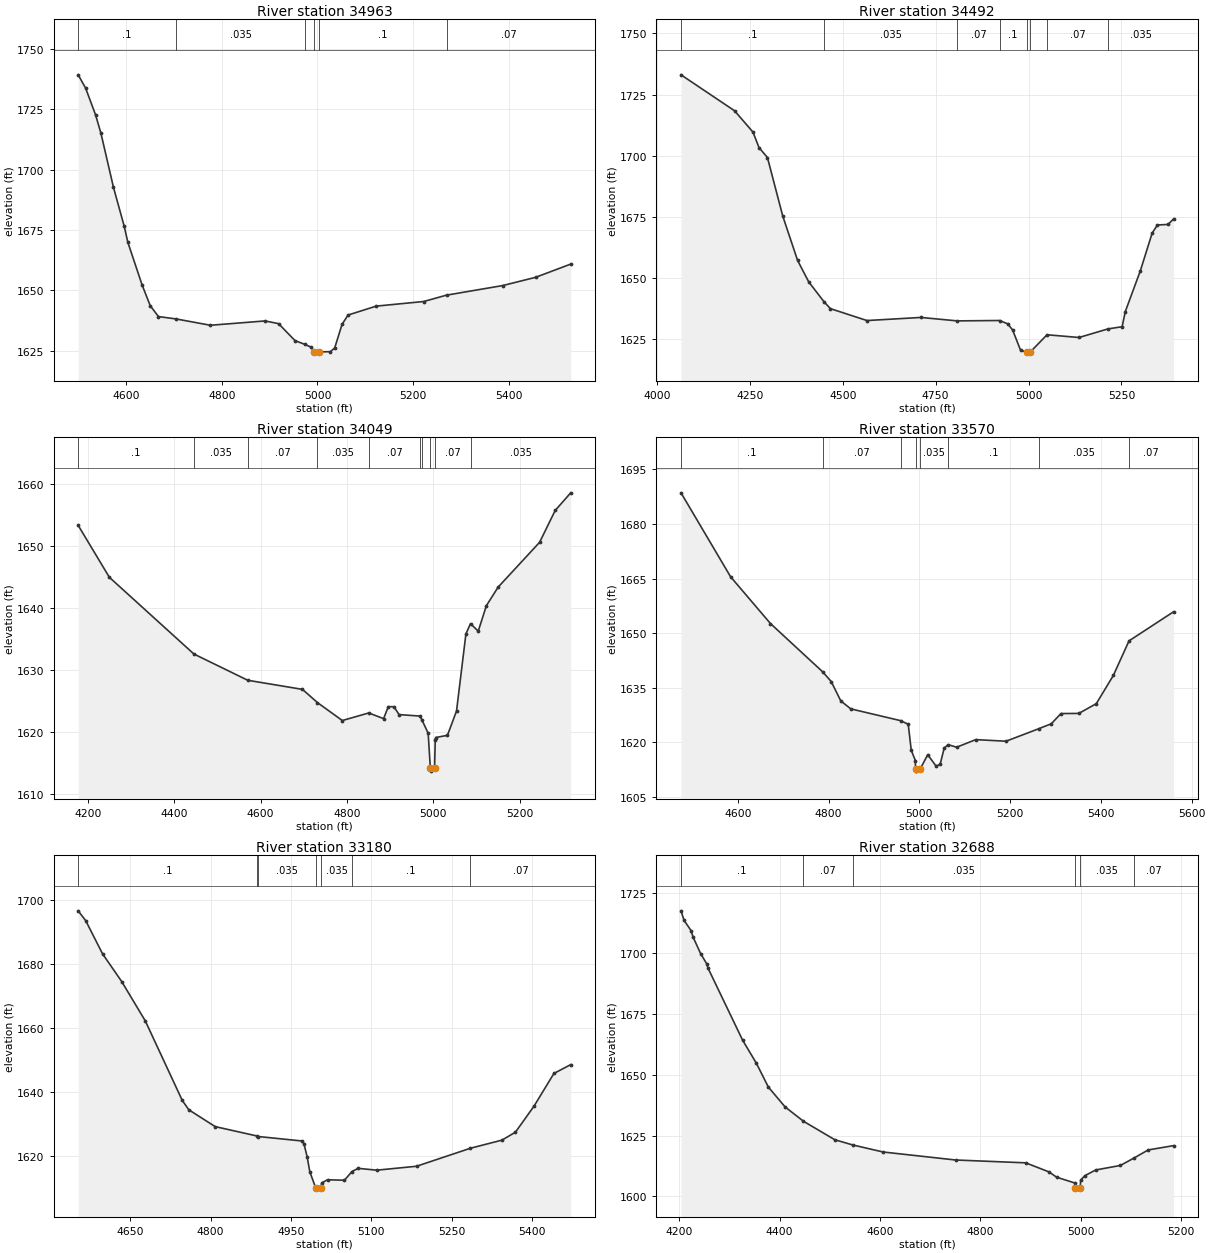
Type RM Length L Ch R = 1,34963,471,471,471
BEGIN DESCRIPTION:
Cherry Creek 63.0
END DESCRIPTION:
XS GIS Cut Line= 3
      1979825.00     13863124.99      1980125.00     13863525.00
      1980637.65     13863656.29
#Sta/Elev= 30
  4499.9 1739.15  4515.5 1733.63  4536.2 1722.63  4547.5 1714.96  4573.7 1692.60
  4596.2 1676.48  4603.7 1669.91  4633.7 1652.16  4650.5 1643.70  4667.7 1639.20
  4705.0 1638.21  4776.2 1635.61  4890.5 1637.40  4918.7 1636.28  4952.9 1629.28
  4973.3 1627.73  4987.0 1626.53  4993.2 1624.59  4993.7 1624.09  5002.7 1624.59
  5026.9 1624.69  5035.9 1626.20  5051.3 1635.98  5063.9 1639.84  5122.6 1643.52
  5221.9 1645.43  5269.6 1648.06  5386.9 1652.02  5455.9 1655.44  5529.1 1660.90
#Mann=6,-1,0
  4499.9     0.1       0  4705.0   0.035       0  4973.3     0.1       0
  4993.2    0.05       0  5002.7     0.1       0  5269.6    0.07       0
Bank Sta=4993.2,5002.7
Exp/Cntr=0.3,0.1

Type RM Length L Ch R = 1,34492,443,443,443
BEGIN DESCRIPTION:
Cherry Creek 62.0
END DESCRIPTION:
XS GIS Cut Line= 3
      1979430.96     13863130.49      1979925.00     13863925.00
      1980224.92     13864174.94
#Sta/Elev= 30
  4064.4 1733.07  4208.7 1718.35  4258.2 1709.62  4274.3 1703.33  4297.1 1699.22
  4338.4 1675.23  4378.3 1657.12  4408.2 1648.36  4449.3 1640.23  4466.6 1637.40
  4565.0 1632.53  4710.4 1633.80  4808.0 1632.39  4922.0 1632.55  4944.0 1631.18
  4957.1 1628.67  4978.8 1620.29  4995.3 1619.70  4995.8 1619.20  5004.9 1619.70
  5049.8 1626.71  5136.0 1625.60  5213.9 1629.11  5252.0 1630.01  5260.5 1636.21
  5301.0 1652.88  5332.8 1668.31  5346.9 1671.63  5375.5 1671.85  5390.4 1674.10
#Mann=8,-1,0
  4064.4     0.1       0  4449.3   0.035       0  4808.0    0.07       0
  4922.0     0.1       0  4995.3    0.05       0  5004.9     0.1       0
  5049.8    0.07       0  5213.9   0.035       0
Bank Sta=4995.3,5004.9
Exp/Cntr=0.3,0.1

Type RM Length L Ch R = 1,34049,479,479,479
BEGIN DESCRIPTION:
Cherry Creek 61.0
END DESCRIPTION:
XS GIS Cut Line= 3
      1979233.87     13863576.00      1979675.00     13864275.00
      1979692.80     13864587.93
#Sta/Elev= 30
  4177.8 1653.31  4250.0 1644.92  4445.7 1632.53  4570.4 1628.29  4697.0 1626.82
  4731.6 1624.69  4789.2 1621.79  4850.3 1623.01  4884.7 1622.10  4895.7 1624.03
  4908.6 1624.02  4920.5 1622.75  4969.0 1622.51  4973.3 1621.91  4987.9 1619.74
  4992.9 1614.12  4993.4 1613.62  5002.7 1614.12  5004.3 1618.66  5005.4 1619.05
  5032.5 1619.40  5053.5 1623.32  5075.3 1635.79  5085.9 1637.43  5103.8 1636.22
  5122.6 1640.33  5149.7 1643.32  5245.8 1650.57  5281.9 1655.71  5317.8 1658.56
#Mann=10,-1,0
  4177.8     0.1       0  4445.7   0.035       0  4570.4    0.07       0
  4731.6   0.035       0  4850.3    0.07       0  4969.0   0.035       0
  4973.3    0.07       0  4992.9    0.05       0  5002.7    0.07       0
  5085.9   0.035       0
Bank Sta=4992.9,5002.7
Exp/Cntr=0.3,0.1

Type RM Length L Ch R = 1,33570,390,390,390
BEGIN DESCRIPTION:
Cherry Creek 60.0
END DESCRIPTION:
XS GIS Cut Line= 3
      1979024.99     13863674.98      1979357.28     13864053.29
      1979432.57     13864630.07
#Sta/Elev= 30
  4474.9 1688.55  4584.2 1665.47  4672.0 1652.63  4787.1 1639.35  4805.8 1636.69
  4827.0 1631.36  4848.9 1629.18  4958.8 1625.94  4975.5 1624.94  4982.2 1617.80
  4991.3 1614.96  4991.6 1612.57  4992.1 1612.07  5001.5 1612.57  5018.5 1616.58
  5036.7 1613.48  5045.8 1613.92  5054.8 1618.43  5063.5 1619.34  5082.2 1618.64
  5124.4 1620.73  5191.0 1620.29  5262.8 1623.71  5290.8 1625.09  5312.0 1627.89
  5351.3 1627.93  5389.9 1630.61  5427.4 1638.35  5462.0 1647.87  5560.1 1655.86
#Mann=8,-1,0
  4474.9     0.1       0  4787.1    0.07       0  4958.8   0.035       0
  4991.6   0.035       0  5001.5   0.035       0  5063.5     0.1       0
  5262.8   0.035       0  5462.0    0.07       0
Bank Sta=4991.6,5001.5
Exp/Cntr=0.3,0.1

Type RM Length L Ch R = 1,33180,492,492,492
BEGIN DESCRIPTION:
Cherry Creek 59.0
END DESCRIPTION:
XS GIS Cut Line= 3
      1978824.99     13863824.99      1979025.00     13864225.00
      1979274.99     13864624.98
#Sta/Elev= 30
  4553.0 1696.64  4567.1 1693.56  4598.4 1683.21  4634.2 1674.51  4678.3 1662.17
  4747.1 1637.33  4759.4 1634.37  4808.6 1629.10  4885.9 1626.19  4888.8 1626.00
  4970.1 1624.61  4974.1 1623.79  4980.2 1619.66  4985.2 1614.94  4995.9 1610.03
  4996.4 1609.53  5005.9 1610.03  5007.4 1611.48  5018.3 1612.46  5049.8 1612.31
  5063.8 1615.04  5075.4 1616.04  5110.0 1615.46  5184.3 1616.69  5284.9 1622.33
  5343.5 1624.86  5368.8 1627.35  5403.6 1635.54  5440.6 1645.74  5471.9 1648.50
#Mann=7,-1,0
  4553.0     0.1       0  4885.9    0.07       0  4888.8   0.035       0
  4995.9   0.035       0  5005.9   0.035       0  5063.8     0.1       0
  5284.9    0.07       0
Bank Sta=4995.9,5005.9
Exp/Cntr=0.3,0.1

Type RM Length L Ch R = 1,32688,421,421,421
BEGIN DESCRIPTION:
Cherry Creek 58.0
END DESCRIPTION:
XS GIS Cut Line= 3
      1978725.00     13863775.04      1978675.00     13864575.00
      1978824.92     13864674.95
#Sta/Elev= 30
  4203.4 1717.53  4209.4 1713.63  4223.5 1709.37  4227.5 1706.71  4242.5 1699.93
  4254.5 1695.78  4257.5 1693.84  4326.1 1664.33  4353.7 1654.78  4377.4 1645.04
  4410.8 1636.85  4447.4 1630.95  4510.0 1623.33  4545.8 1621.18  4606.2 1618.29
  4750.5 1615.00  4890.4 1613.83  4936.9 1610.10  4951.9 1607.93  4988.0 1605.56
  4989.0 1603.51  4989.5 1603.01  4999.0 1603.51  5000.0 1606.70  5008.3 1608.54
  5029.9 1610.89  5079.1 1612.75  5106.4 1615.82  5134.5 1619.13  5185.1 1620.91
#Mann=6,-1,0
  4203.4     0.1       0  4447.4    0.07       0  4545.8   0.035       0
  4989.0   0.035       0  4999.0   0.035       0  5106.4    0.07       0
Bank Sta=4989,4999
Exp/Cntr=0.3,0.1