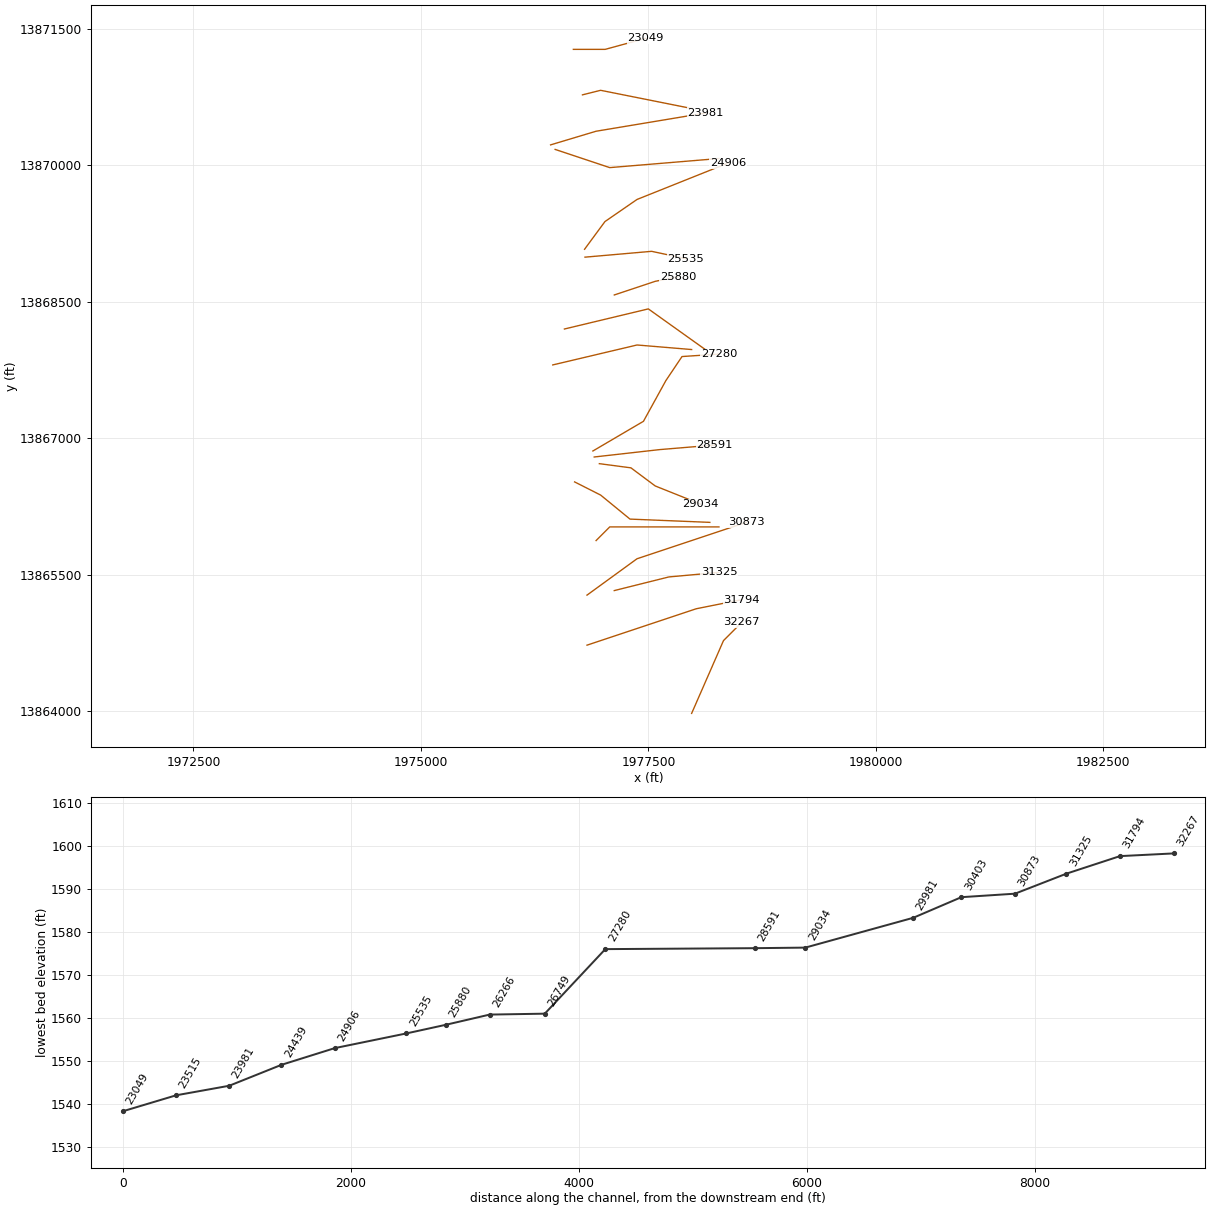
HEC-RAS study Cherry Creek.prj: Cherry Creek Base Level Engineering

--- Cherry Creek.g01 (geometry) --- (continued)

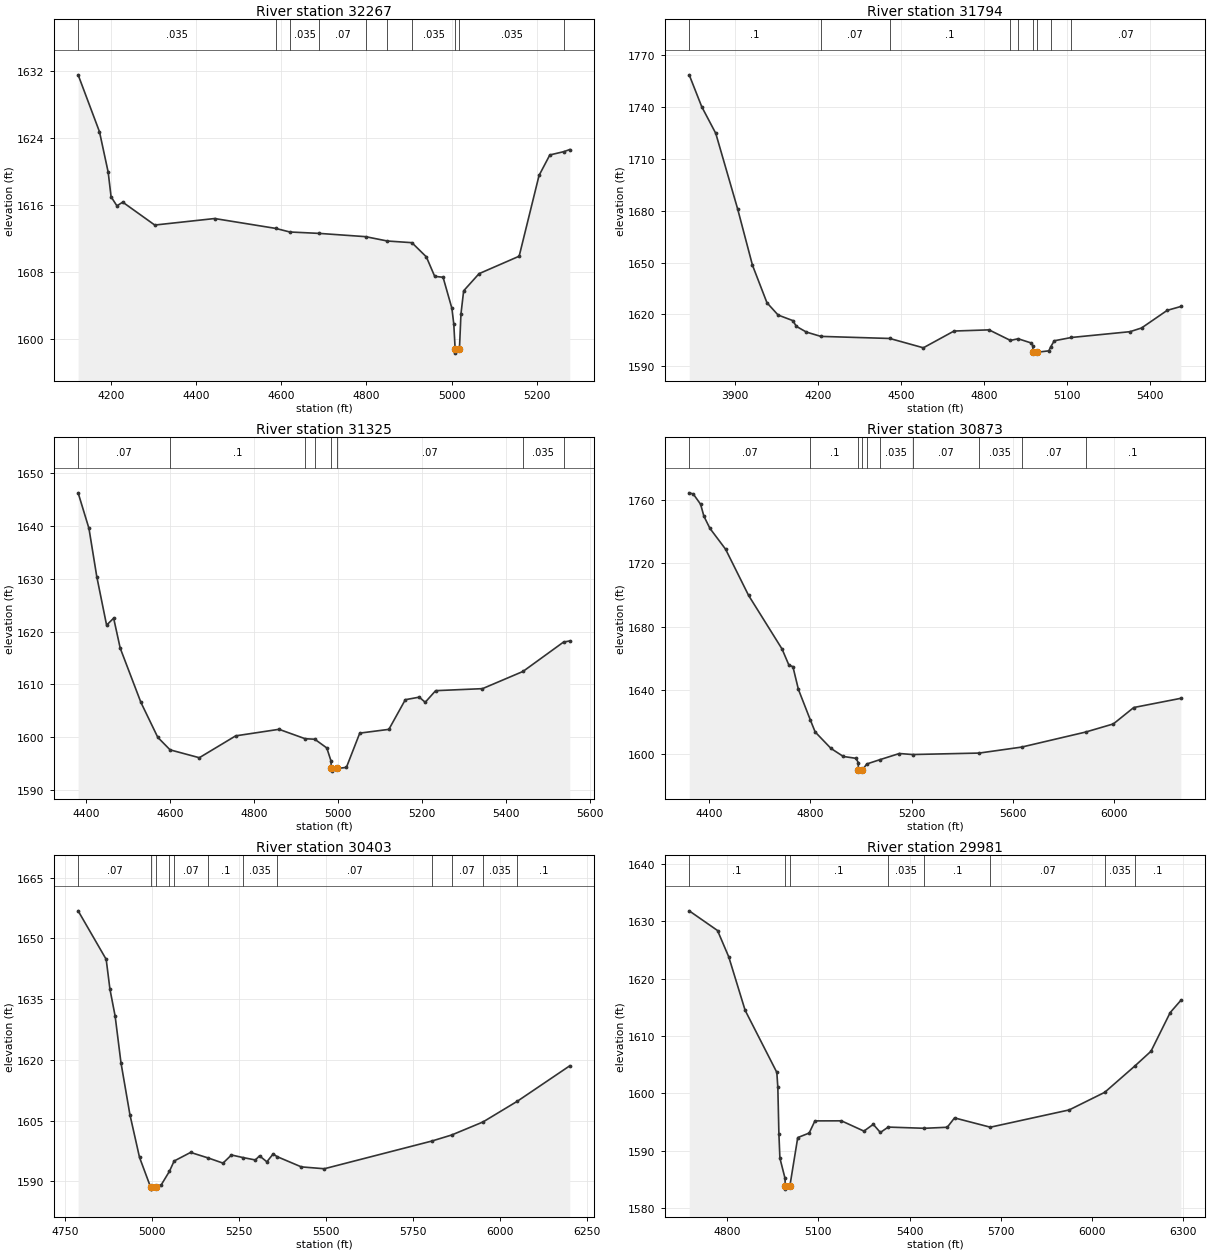
Type RM Length L Ch R = 1,32267,473,473,473
BEGIN DESCRIPTION:
Cherry Creek 57.0
END DESCRIPTION:
XS GIS Cut Line= 3
      1977975.01     13863975.02      1978325.00     13864775.00
      1978524.98     13864974.98
#Sta/Elev= 30
  4122.0 1631.59  4172.2 1624.78  4192.7 1619.93  4199.5 1616.99  4213.2 1615.91
  4226.9 1616.35  4302.2 1613.61  4443.0 1614.39  4586.4 1613.21  4619.7 1612.78
  4689.1 1612.61  4797.9 1612.22  4849.0 1611.70  4906.8 1611.50  4940.8 1609.80
  4960.4 1607.47  4980.1 1607.36  5000.9 1603.63  5005.3 1601.75  5008.5 1598.78
  5009.0 1598.28  5018.6 1598.78  5022.2 1602.98  5028.5 1605.74  5064.7 1607.79
  5159.0 1609.88  5205.8 1619.55  5231.1 1622.00  5264.5 1622.40  5278.0 1622.65
#Mann=10,-1,0
  4122.0   0.035       0  4586.4    0.07       0  4619.7   0.035       0
  4689.1    0.07       0  4797.9   0.035       0  4849.0    0.07       0
  4906.8   0.035       0  5008.5   0.035       0  5018.6   0.035       0
  5264.5    0.07       0
Bank Sta=5008.5,5018.6
Exp/Cntr=0.3,0.1

Type RM Length L Ch R = 1,31794,469,469,469
BEGIN DESCRIPTION:
Cherry Creek 56.0
END DESCRIPTION:
XS GIS Cut Line= 3
      1976825.04     13864725.01      1978025.00     13865125.00
      1978525.03     13865225.01
#Sta/Elev= 30
  3735.4 1758.54  3780.7 1740.10  3831.3 1724.72  3910.3 1681.02  3963.9 1648.44
  4016.1 1626.79  4056.4 1619.67  4109.6 1616.45  4122.2 1613.13  4158.4 1609.83
  4210.5 1607.33  4459.6 1606.12  4580.7 1600.73  4691.4 1610.42  4817.8 1611.10
  4895.1 1604.99  4922.8 1605.96  4969.7 1603.54  4976.0 1601.81  4976.5 1598.15
  4977.0 1597.65  4991.0 1598.15  5033.5 1598.97  5041.2 1601.47  5053.3 1604.79
  5115.4 1606.70  5326.7 1610.05  5368.4 1612.19  5461.0 1622.38  5510.2 1624.61
#Mann=9,-1,0
  3735.4     0.1       0  4210.5    0.07       0  4459.6     0.1       0
  4895.1   0.035       0  4922.8    0.07       0  4976.5    0.05       0
  4991.0    0.07       0  5041.2   0.035       0  5115.4    0.07       0
Bank Sta=4976.5,4991
Exp/Cntr=0.3,0.1

Type RM Length L Ch R = 1,31325,452,452,452
BEGIN DESCRIPTION:
Cherry Creek 55.0
END DESCRIPTION:
XS GIS Cut Line= 3
      1977124.98     13865325.00      1977725.00     13865475.00
      1978275.05     13865525.00
#Sta/Elev= 30
  4381.5 1646.29  4407.3 1639.55  4425.9 1630.43  4449.3 1621.23  4466.1 1622.55
  4481.7 1616.88  4531.0 1606.60  4571.2 1599.98  4600.5 1597.61  4670.1 1596.12
  4756.7 1600.26  4859.9 1601.50  4922.1 1599.72  4945.1 1599.62  4973.7 1597.97
  4983.6 1595.53  4984.5 1594.08  4985.0 1593.58  4999.0 1594.08  5020.4 1594.29
  5052.2 1600.78  5121.5 1601.49  5160.7 1607.11  5193.8 1607.59  5208.1 1606.62
  5232.9 1608.82  5344.4 1609.20  5440.9 1612.46  5537.4 1618.02  5552.3 1618.24
#Mann=8,-1,0
  4381.5    0.07       0  4600.5     0.1       0  4922.1   0.035       0
  4945.1    0.07       0  4984.5    0.05       0  4999.0    0.07       0
  5440.9   0.035       0  5537.4    0.07       0
Bank Sta=4984.5,4999
Exp/Cntr=0.3,0.1

Type RM Length L Ch R = 1,30873,470,470,470
BEGIN DESCRIPTION:
Cherry Creek 54.0
END DESCRIPTION:
XS GIS Cut Line= 3
      1976824.96     13865274.97      1977375.00     13865675.00
      1978574.97     13866074.99
#Sta/Elev= 30
  4320.1 1764.28  4336.2 1763.55  4365.3 1757.06  4378.2 1749.60  4401.9 1741.94
  4464.1 1728.75  4555.1 1699.64  4687.5 1665.86  4714.6 1655.71  4730.4 1654.75
  4752.2 1640.41  4799.4 1621.15  4818.5 1613.60  4880.8 1603.25  4929.8 1598.16
  4979.6 1597.00  4989.1 1594.31  4989.2 1589.42  4989.7 1588.92  5003.8 1589.42
  5022.9 1593.44  5073.7 1596.09  5151.5 1600.02  5203.9 1599.38  5467.5 1600.30
  5635.3 1604.07  5888.3 1613.53  5998.2 1618.67  6078.8 1629.00  6265.1 1634.80
#Mann=10,-1,0
  4320.1    0.07       0  4799.4     0.1       0  4989.2    0.05       0
  5003.8     0.1       0  5022.9    0.07       0  5073.7   0.035       0
  5203.9    0.07       0  5467.5   0.035       0  5635.3    0.07       0
  5888.3     0.1       0
Bank Sta=4989.2,5003.8
Exp/Cntr=0.3,0.1

Type RM Length L Ch R = 1,30403,422,422,422
BEGIN DESCRIPTION:
Cherry Creek 53.0
END DESCRIPTION:
XS GIS Cut Line= 3
      1976925.02     13865875.02      1977075.00     13866025.00
      1978274.99     13866025.00
#Sta/Elev= 30
  4788.1 1656.80  4868.7 1644.82  4879.5 1637.45  4894.4 1630.82  4911.1 1619.35
  4936.8 1606.52  4964.4 1595.96  4996.2 1588.61  4996.7 1588.11  5010.8 1588.61
  5027.2 1589.22  5050.3 1592.50  5063.9 1595.05  5111.2 1597.17  5162.5 1595.78
  5204.2 1594.53  5228.5 1596.54  5261.0 1595.91  5297.2 1595.31  5309.2 1596.33
  5330.2 1594.85  5348.2 1596.79  5359.6 1596.13  5429.2 1593.60  5495.2 1593.14
  5803.7 1599.97  5861.0 1601.47  5950.8 1604.68  6049.4 1609.79  6200.2 1618.55
#Mann=12,-1,0
  4788.1    0.07       0  4996.2    0.05       0  5010.8    0.07       0
  5050.3     0.1       0  5063.9    0.07       0  5162.5     0.1       0
  5261.0   0.035       0  5359.6    0.07       0  5803.7   0.035       0
  5861.0    0.07       0  5950.8   0.035       0  6049.4     0.1       0
Bank Sta=4996.2,5010.8
Exp/Cntr=0.3,0.1

Type RM Length L Ch R = 1,29981,947,947,947
BEGIN DESCRIPTION:
Cherry Creek 52.0
END DESCRIPTION:
XS GIS Cut Line= 4
      1976688.97     13866519.65      1976975.00     13866375.00
      1977297.61     13866110.83      1978174.98     13866075.00
#Sta/Elev= 30
  4675.7 1631.81  4768.8 1628.38  4805.7 1623.79  4859.5 1614.48  4963.7 1603.66
  4967.0 1601.03  4970.5 1592.94  4973.8 1588.71  4990.6 1585.21  4991.4 1583.82
  4991.9 1583.32  5006.4 1583.82  5032.4 1592.30  5069.9 1593.09  5088.9 1595.21
  5175.9 1595.22  5249.9 1593.43  5280.6 1594.61  5303.9 1593.19  5329.6 1594.13
  5448.8 1593.92  5523.7 1594.10  5547.7 1595.73  5665.3 1594.11  5924.4 1597.12
  6041.3 1600.19  6140.1 1604.77  6193.2 1607.34  6256.3 1614.08  6291.3 1616.21
#Mann=8,-1,0
  4675.7     0.1       0  4991.4    0.05       0  5006.4     0.1       0
  5329.6   0.035       0  5448.8     0.1       0  5665.3    0.07       0
  6041.3   0.035       0  6140.1     0.1       0
Bank Sta=4991.4,5006.4
Exp/Cntr=0.3,0.1

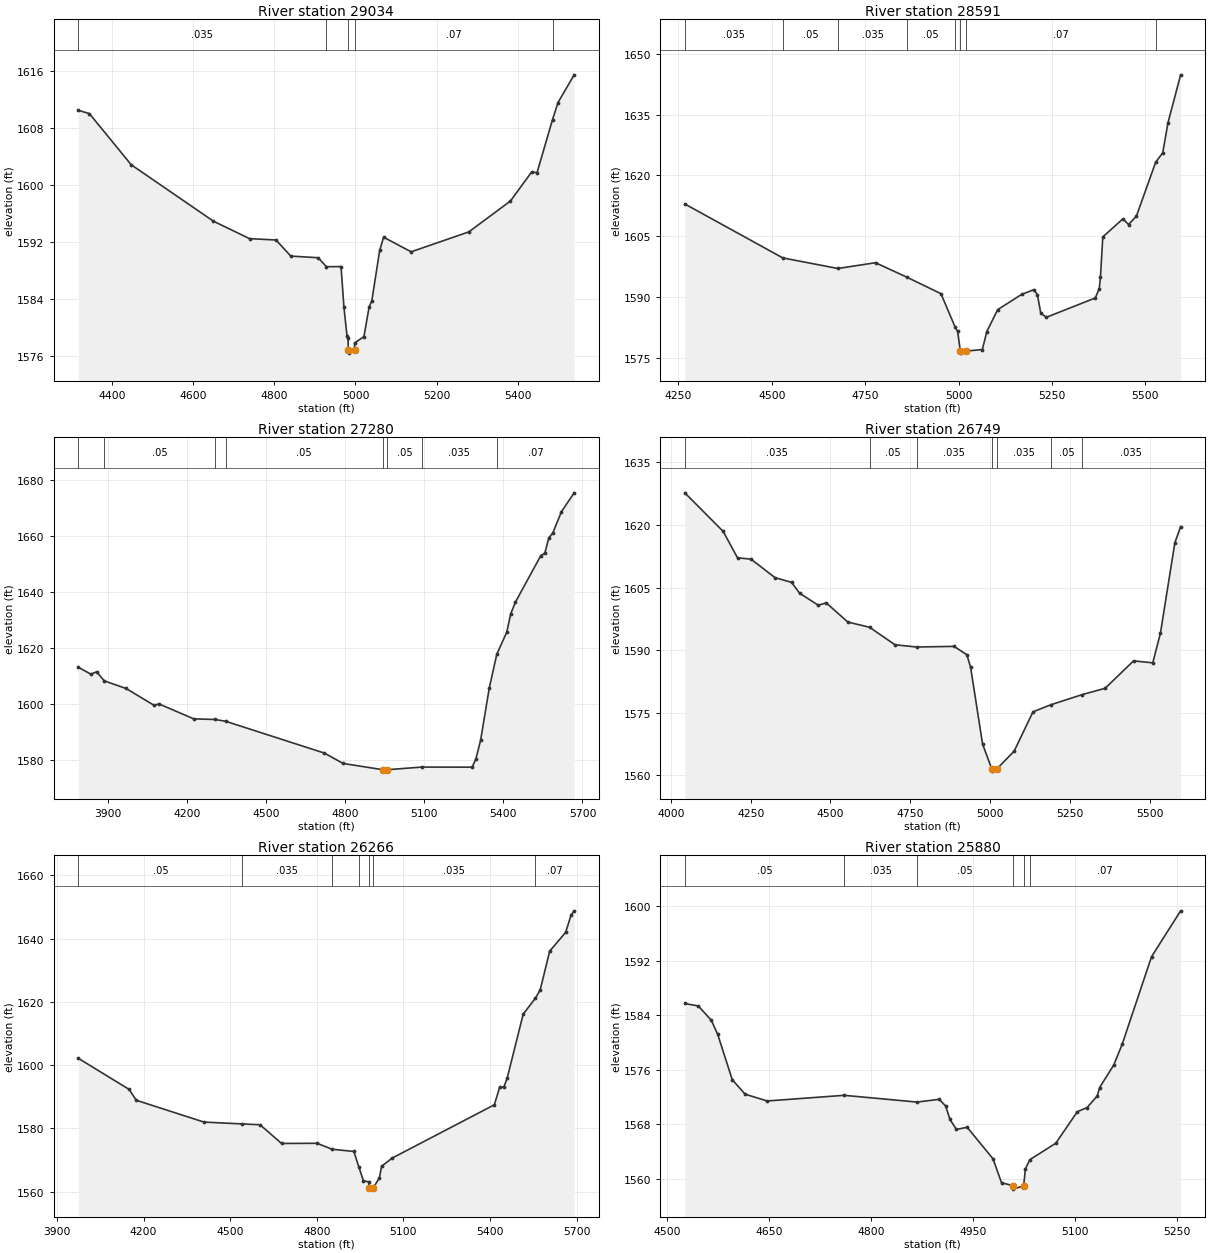
Type RM Length L Ch R = 1,29034,443,443,443
BEGIN DESCRIPTION:
Cherry Creek 51.0
END DESCRIPTION:
XS GIS Cut Line= 4
      1976960.99     13866720.32      1977307.95     13866674.29
      1977575.00     13866475.00      1978074.97     13866275.01
#Sta/Elev= 30
  4317.2 1610.50  4344.5 1610.03  4447.5 1602.85  4650.1 1594.92  4739.1 1592.47
  4804.3 1592.28  4840.7 1590.02  4908.1 1589.79  4928.5 1588.53  4964.5 1588.55
  4971.7 1582.81  4979.2 1578.81  4981.6 1578.52  4982.6 1576.89  4983.1 1576.39
  4997.8 1576.89  4997.9 1577.81  5020.9 1578.71  5033.8 1582.90  5040.3 1583.73
  5059.7 1590.81  5069.4 1592.67  5137.2 1590.62  5279.4 1593.42  5381.8 1597.75
  5434.5 1601.86  5447.4 1601.73  5485.6 1609.19  5499.1 1611.59  5538.9 1615.48
#Mann=5,-1,0
  4317.2   0.035       0  4928.5    0.07       0  4982.6    0.05       0
  4997.8    0.07       0  5485.6     0.1       0
Bank Sta=4982.6,4997.8
Exp/Cntr=0.3,0.1

Type RM Length L Ch R = 1,28591,1311,1311,1311
BEGIN DESCRIPTION:
Cherry Creek 50.0
END DESCRIPTION:
XS GIS Cut Line= 3
      1976904.33     13866793.73      1977625.00     13866875.00
      1978224.98     13866925.00
#Sta/Elev= 30
  4267.1 1612.99  4529.5 1599.70  4676.9 1597.10  4777.6 1598.52  4862.2 1594.93
  4952.8 1590.90  4990.9 1582.64  4997.4 1581.61  5004.8 1576.76  5005.3 1576.26
  5020.0 1576.76  5063.6 1577.15  5075.6 1581.57  5104.7 1586.97  5169.0 1590.73
  5202.1 1591.90  5211.1 1590.60  5220.1 1586.05  5235.2 1585.09  5365.9 1589.84
  5376.7 1592.15  5379.8 1595.04  5386.1 1604.88  5439.9 1609.32  5454.9 1607.92
  5476.0 1609.98  5527.6 1623.27  5546.5 1625.57  5560.3 1632.88  5594.4 1644.78
#Mann=8,-1,0
  4267.1   0.035       0  4529.5    0.05       0  4676.9   0.035       0
  4862.2    0.05       0  4990.9    0.07       0  5004.8    0.05       0
  5020.0    0.07       0  5527.6     0.1       0
Bank Sta=5004.8,5020
Exp/Cntr=0.3,0.1

Type RM Length L Ch R = 1,27280,531,531,531
BEGIN DESCRIPTION:
Cherry Creek 49.0
END DESCRIPTION:
XS GIS Cut Line= 5
      1976889.96     13866859.68      1977445.55     13867186.09
      1977692.07     13867634.00      1977869.16     13867897.89
      1978275.00     13867925.00
#Sta/Elev= 30
  3788.3 1613.16  3835.9 1610.67  3857.5 1611.53  3886.8 1608.29  3969.2 1605.58
  4076.6 1599.50  4093.4 1600.09  4225.6 1594.73  4307.0 1594.49  4346.7 1593.86
  4720.6 1582.51  4792.5 1578.78  4943.4 1576.54  4943.9 1576.04  4958.7 1576.54
  5090.8 1577.49  5281.7 1577.45  5295.7 1580.33  5313.7 1587.05  5346.8 1605.84
  5375.2 1617.83  5412.9 1625.69  5428.0 1632.25  5446.0 1636.48  5542.2 1653.08
  5557.3 1653.92  5572.3 1659.34  5587.3 1661.11  5620.4 1668.75  5668.5 1675.49
#Mann=8,-1,0
  3788.3   0.035       0  3886.8    0.05       0  4307.0   0.035       0
  4346.7    0.05       0  4943.4    0.05       0  4958.7    0.05       0
  5090.8   0.035       0  5375.2    0.07       0
Bank Sta=4943.4,4958.7
Exp/Cntr=0.3,0.1

Type RM Length L Ch R = 1,26749,483,483,483
BEGIN DESCRIPTION:
Cherry Creek 48.0
END DESCRIPTION:
XS GIS Cut Line= 3
      1976448.81     13867805.71      1977375.00     13868025.00
      1977975.02     13867975.00
#Sta/Elev= 30
  4043.5 1627.72  4163.8 1618.48  4208.7 1612.15  4251.1 1611.83  4325.8 1607.42
  4378.2 1606.26  4403.4 1603.66  4462.0 1600.78  4486.6 1601.36  4554.5 1596.76
  4622.5 1595.51  4702.4 1591.31  4769.7 1590.78  4887.4 1590.93  4927.5 1588.92
  4939.1 1585.95  4976.8 1567.51  5005.6 1561.54  5006.1 1561.04  5021.1 1561.54
  5075.6 1565.82  5134.7 1575.24  5189.8 1576.92  5288.9 1579.37  5360.9 1580.89
  5449.9 1587.46  5510.1 1586.98  5534.2 1594.13  5579.3 1615.74  5597.4 1619.64
#Mann=7,-1,0
  4043.5   0.035       0  4622.5    0.05       0  4769.7   0.035       0
  5005.6   0.035       0  5021.1   0.035       0  5189.8    0.05       0
  5288.9   0.035       0
Bank Sta=5005.6,5021.1
Exp/Cntr=0.3,0.1

Type RM Length L Ch R = 1,26266,386,386,386
BEGIN DESCRIPTION:
Cherry Creek 47.0
END DESCRIPTION:
XS GIS Cut Line= 3
      1976576.98     13868200.71      1977499.04     13868421.77
      1978124.97     13867975.02
#Sta/Elev= 30
  3974.3 1602.16  4150.2 1592.34  4174.9 1588.91  4409.5 1582.01  4542.7 1581.43
  4603.7 1581.16  4678.2 1575.26  4801.1 1575.31  4853.4 1573.43  4928.6 1572.73
  4945.5 1567.89  4961.8 1563.45  4980.2 1563.13  4981.0 1561.33  4981.5 1560.83
  4996.5 1561.33  5017.1 1564.42  5024.6 1568.06  5061.3 1570.64  5415.1 1587.48
  5433.5 1593.02  5448.2 1593.13  5459.3 1595.80  5515.0 1616.12  5556.9 1621.11
  5573.6 1623.70  5606.8 1636.02  5662.1 1641.97  5680.5 1647.33  5691.5 1648.76
#Mann=7,-1,0
  3974.3    0.05       0  4542.7   0.035       0  4853.4    0.05       0
  4945.5   0.035       0  4981.0   0.035       0  4996.5   0.035       0
  5556.9    0.07       0
Bank Sta=4981,4996.5
Exp/Cntr=0.3,0.1

Type RM Length L Ch R = 1,25880,345,345,345
BEGIN DESCRIPTION:
Cherry Creek 46.0
END DESCRIPTION:
XS GIS Cut Line= 3
      1977124.99     13868575.00      1977575.00     13868725.00
      1977825.00     13868775.00
#Sta/Elev= 30
  4526.0 1585.70  4546.0 1585.33  4565.0 1583.23  4574.4 1581.17  4595.8 1574.51
  4614.8 1572.38  4647.2 1571.39  4760.4 1572.22  4867.5 1571.23  4900.2 1571.63
  4909.7 1570.65  4916.0 1568.69  4925.5 1567.21  4941.3 1567.53  4979.3 1562.91
  4991.9 1559.39  5008.9 1558.95  5009.4 1558.45  5024.4 1558.95  5027.0 1561.43
  5033.5 1562.77  5071.7 1565.19  5103.4 1569.82  5117.6 1570.42  5132.9 1572.15
  5136.0 1573.34  5157.0 1576.68  5169.5 1579.76  5212.5 1592.56  5255.3 1599.30
#Mann=6,-1,0
  4526.0    0.05       0  4760.4   0.035       0  4867.5    0.05       0
  5008.9    0.05       0  5024.4    0.05       0  5033.5    0.07       0
Bank Sta=5008.9,5024.4
Exp/Cntr=0.3,0.1

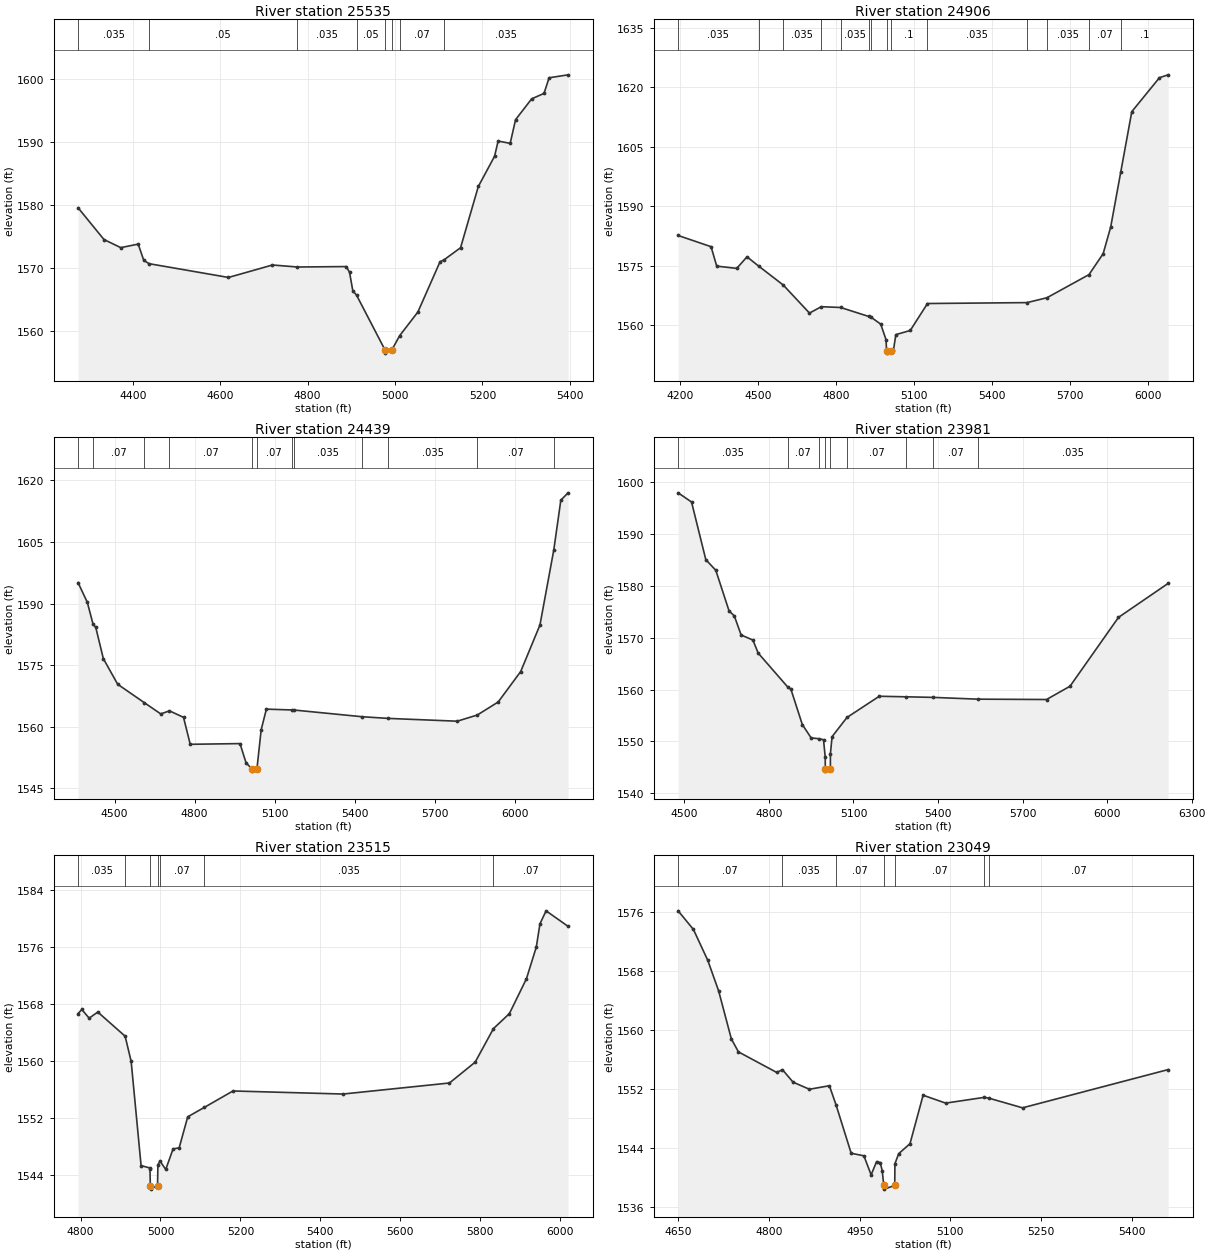
Type RM Length L Ch R = 1,25535,629,629,629
BEGIN DESCRIPTION:
Cherry Creek 45.0
END DESCRIPTION:
XS GIS Cut Line= 3
      1976802.91     13868990.56      1977535.05     13869054.70
      1977912.50     13868974.13
#Sta/Elev= 30
  4274.9 1579.56  4334.2 1574.51  4372.6 1573.22  4412.5 1573.78  4425.2 1571.21
  4437.2 1570.67  4619.0 1568.48  4719.7 1570.46  4776.8 1570.14  4888.3 1570.21
  4895.9 1569.31  4903.4 1566.37  4912.0 1565.66  4977.1 1556.95  4977.6 1556.45
  4992.7 1556.95  5010.6 1559.23  5052.2 1562.98  5102.9 1570.97  5112.1 1571.28
  5149.9 1573.21  5190.5 1582.94  5227.7 1587.75  5235.8 1590.16  5263.4 1589.80
  5275.7 1593.56  5312.5 1596.87  5340.8 1597.74  5352.4 1600.22  5395.8 1600.69
#Mann=8,-1,0
  4274.9   0.035       0  4437.2    0.05       0  4776.8   0.035       0
  4912.0    0.05       0  4977.1    0.05       0  4992.7    0.05       0
  5010.6    0.07       0  5112.1   0.035       0
Bank Sta=4977.1,4992.7
Exp/Cntr=0.3,0.1

Type RM Length L Ch R = 1,24906,467,467,467
BEGIN DESCRIPTION:
Cherry Creek 44.0
END DESCRIPTION:
XS GIS Cut Line= 4
      1976798.15     13869077.18      1977022.09     13869381.65
      1977375.00     13869625.00      1978375.03     13870025.01
#Sta/Elev= 30
  4193.6 1582.65  4320.2 1579.83  4341.9 1574.94  4418.9 1574.36  4458.3 1577.28
  4502.7 1574.97  4597.8 1570.17  4698.5 1563.11  4743.8 1564.72  4818.5 1564.52
  4925.4 1562.28  4935.7 1562.05  4972.4 1560.33  4993.0 1556.38  4994.7 1553.53
  4995.2 1553.03  5010.8 1553.53  5021.2 1553.71  5030.5 1557.69  5085.9 1558.73
  5152.1 1565.52  5534.6 1565.75  5611.2 1566.97  5773.0 1572.80  5827.4 1578.06
  5856.5 1584.81  5895.2 1598.67  5937.5 1613.83  6043.9 1622.38  6077.3 1623.10
#Mann=14,-1,0
  4193.6   0.035       0  4502.7    0.05       0  4597.8   0.035       0
  4743.8    0.07       0  4818.5   0.035       0  4925.4    0.07       0
  4935.7     0.1       0  4994.7    0.05       0  5010.8     0.1       0
  5152.1   0.035       0  5534.6    0.07       0  5611.2   0.035       0
  5773.0    0.07       0  5895.2     0.1       0
Bank Sta=4994.7,5010.8
Exp/Cntr=0.3,0.1

Type RM Length L Ch R = 1,24439,458,458,458
BEGIN DESCRIPTION:
Cherry Creek 43.0
END DESCRIPTION:
XS GIS Cut Line= 3
      1976475.04     13870174.99      1977075.00     13869975.00
      1978275.03     13870075.00
#Sta/Elev= 30
  4363.1 1595.10  4397.9 1590.29  4419.3 1584.97  4429.5 1584.19  4457.9 1576.57
  4511.7 1570.32  4612.1 1565.81  4673.0 1563.10  4705.8 1563.84  4758.4 1562.26
  4783.6 1555.69  4970.2 1555.86  4992.8 1551.17  5015.5 1549.65  5016.0 1549.15
  5033.5 1549.65  5049.5 1559.24  5069.0 1564.26  5163.7 1564.06  5171.5 1564.05
  5427.6 1562.41  5526.2 1562.00  5784.2 1561.32  5859.3 1562.82  5937.8 1566.00
  6022.1 1573.42  6094.3 1584.76  6146.0 1602.99  6172.6 1615.20  6199.7 1616.98
#Mann=12,-1,0
  4363.1   0.035       0  4419.3    0.07       0  4612.1   0.035       0
  4705.8    0.07       0  5015.5    0.05       0  5033.5    0.07       0
  5163.7    0.07       0  5171.5   0.035       0  5427.6    0.07       0
  5526.2   0.035       0  5859.3    0.07       0  6146.0     0.1       0
Bank Sta=5015.5,5033.5
Exp/Cntr=0.3,0.1

Type RM Length L Ch R = 1,23981,466,466,466
BEGIN DESCRIPTION:
Cherry Creek 42.0
END DESCRIPTION:
XS GIS Cut Line= 3
      1976425.01     13870225.00      1976925.00     13870375.00
      1978125.04     13870575.01
#Sta/Elev= 30
  4478.0 1597.92  4525.6 1596.15  4576.2 1585.04  4611.6 1583.00  4658.6 1575.18
  4677.4 1574.19  4701.5 1570.53  4743.2 1569.55  4762.0 1567.04  4866.8 1560.50
  4877.9 1560.11  4918.6 1553.27  4949.9 1550.69  4977.1 1550.54  4993.8 1550.34
  5000.0 1546.93  5000.1 1544.79  5000.6 1544.29  5018.2 1544.79  5018.3 1547.68
  5024.3 1550.94  5077.0 1554.63  5191.6 1558.72  5287.8 1558.61  5382.7 1558.50
  5540.4 1558.16  5785.0 1558.09  5868.4 1560.65  6040.4 1573.92  6216.6 1580.47
#Mann=9,-1,0
  4478.0   0.035       0  4866.8    0.07       0  4977.1     0.1       0
  5000.1    0.05       0  5018.2     0.1       0  5077.0    0.07       0
  5287.8   0.035       0  5382.7    0.07       0  5540.4   0.035       0
Bank Sta=5000.1,5018.2
Exp/Cntr=0.3,0.1

Type RM Length L Ch R = 1,23515,466,466,466
BEGIN DESCRIPTION:
Cherry Creek 41.0
END DESCRIPTION:
XS GIS Cut Line= 3
      1976775.04     13870775.01      1976975.00     13870825.00
      1977974.98     13870625.00
#Sta/Elev= 30
  4793.8 1566.71  4803.2 1567.29  4821.6 1566.07  4843.2 1566.93  4911.6 1563.54
  4926.7 1559.99  4951.5 1545.37  4973.1 1545.05  4973.8 1544.88  4974.6 1542.57
  4975.1 1542.07  4992.7 1542.57  4993.6 1545.48  4998.8 1546.01  5013.2 1544.83
  5031.5 1547.71  5046.8 1547.87  5068.2 1552.22  5109.3 1553.53  5181.4 1555.85
  5456.7 1555.42  5723.0 1556.97  5787.2 1559.89  5833.1 1564.61  5872.9 1566.71
  5915.6 1571.61  5940.2 1576.05  5949.4 1579.32  5964.7 1581.14  6019.7 1578.96
#Mann=7,-1,0
  4793.8   0.035       0  4911.6     0.1       0  4974.6    0.05       0
  4992.7     0.1       0  4998.8    0.07       0  5109.3   0.035       0
  5833.1    0.07       0
Bank Sta=4974.6,4992.7
Exp/Cntr=0.3,0.1

Type RM Length L Ch R = 1,23049,485,485,485
BEGIN DESCRIPTION:
Cherry Creek 40.0
END DESCRIPTION:
XS GIS Cut Line= 3
      1976675.03     13871275.00      1977025.00     13871275.00
      1977468.60     13871396.30
#Sta/Elev= 30
  4650.0 1576.13  4675.3 1573.60  4699.0 1569.41  4717.0 1565.25  4738.0 1558.74
  4749.7 1556.99  4813.0 1554.20  4822.4 1554.58  4840.0 1552.88  4867.0 1551.92
  4900.0 1552.40  4911.2 1549.75  4936.0 1543.24  4957.0 1542.89  4969.0 1540.31
  4978.0 1542.10  4984.0 1541.97  4987.3 1540.88  4989.9 1538.87  4990.4 1538.37
  5008.0 1538.87  5008.3 1541.81  5014.5 1543.18  5033.2 1544.53  5054.9 1551.11
  5092.2 1550.04  5156.0 1550.82  5163.8 1550.71  5219.2 1549.40  5459.9 1554.59
#Mann=7,-1,0
  4650.0    0.07       0  4822.4   0.035       0  4911.2    0.07       0
  4989.9    0.05       0  5008.0    0.07       0  5156.0   0.035       0
  5163.8    0.07       0
Bank Sta=4989.9,5008
Exp/Cntr=0.3,0.1