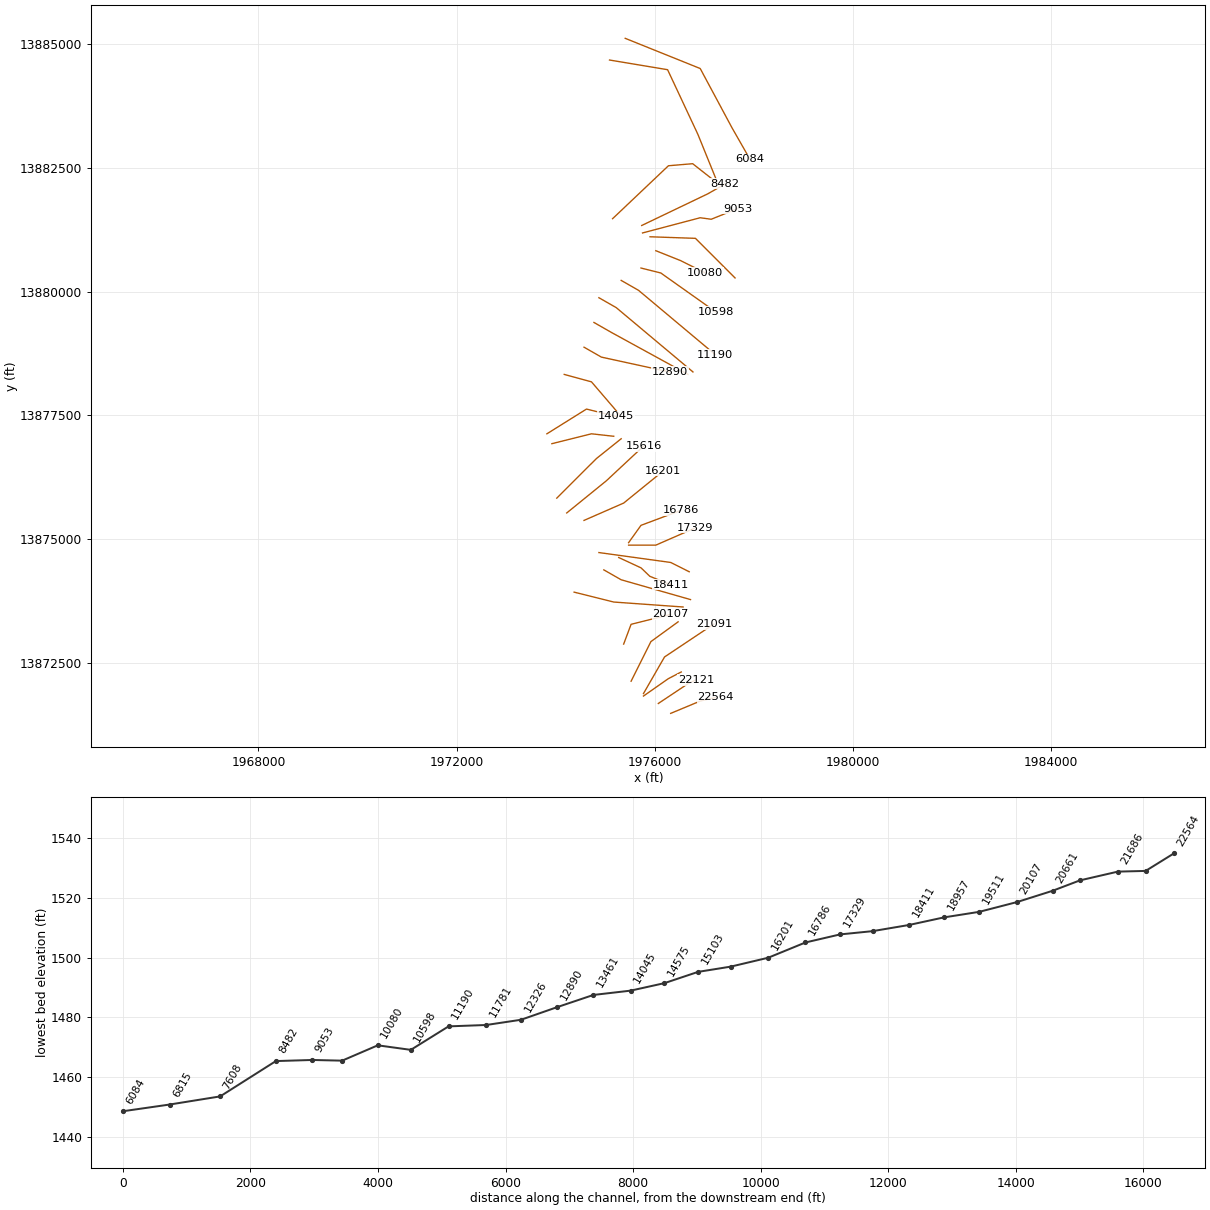
HEC-RAS study Cherry Creek.prj: Cherry Creek Base Level Engineering

--- Cherry Creek.g01 (geometry) --- (continued)

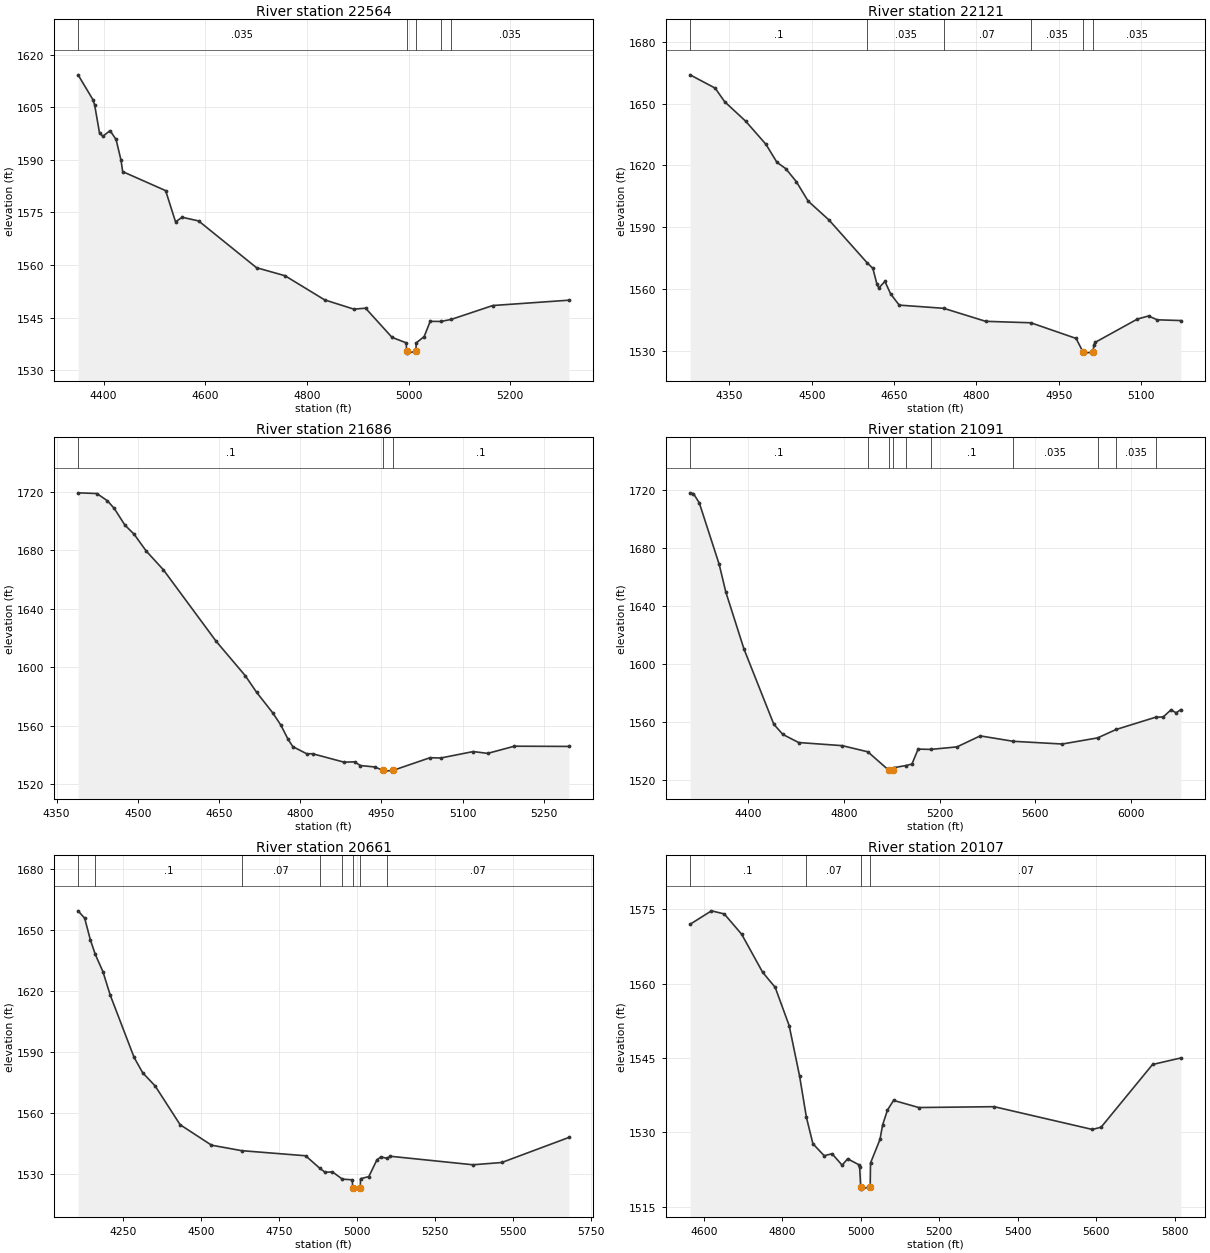
Type RM Length L Ch R = 1,22564,443,443,443
BEGIN DESCRIPTION:
Cherry Creek 39.0
END DESCRIPTION:
XS GIS Cut Line= 3
      1976325.03     13871475.01      1976925.00     13871725.00
      1977231.80     13871798.25
#Sta/Elev= 30
  4350.0 1614.23  4379.2 1607.14  4382.5 1605.71  4392.2 1597.62  4398.7 1596.69
  4412.9 1598.31  4424.7 1595.80  4434.5 1589.84  4437.7 1586.62  4522.2 1581.20
  4541.7 1572.30  4554.7 1573.60  4587.1 1572.55  4701.0 1559.21  4757.0 1556.92
  4835.0 1550.03  4892.4 1547.39  4915.5 1547.66  4967.5 1539.34  4995.6 1537.77
  4996.1 1535.34  4996.6 1534.84  5014.4 1535.34  5015.2 1537.76  5030.8 1539.57
  5042.6 1543.91  5063.5 1543.87  5083.6 1544.44  5165.7 1548.42  5315.4 1549.94
#Mann=5,-1,0
  4350.0   0.035       0  4996.1   0.035       0  5014.4   0.035       0
  5063.5    0.07       0  5083.6   0.035       0
Bank Sta=4996.1,5014.4
Exp/Cntr=0.3,0.1

Type RM Length L Ch R = 1,22121,435,435,435
BEGIN DESCRIPTION:
Cherry Creek 38.0
END DESCRIPTION:
XS GIS Cut Line= 3
      1976074.98     13871674.98      1976675.00     13872075.00
      1976831.15     13872149.57
#Sta/Elev= 30
  4278.4 1663.96  4324.1 1657.51  4341.4 1650.92  4379.9 1641.42  4416.7 1630.24
  4436.6 1621.54  4452.7 1618.46  4471.9 1612.19  4493.5 1602.71  4531.4 1593.58
  4601.1 1572.76  4611.4 1570.12  4618.6 1562.68  4622.2 1560.58  4633.4 1563.76
  4643.8 1557.70  4659.4 1552.27  4740.5 1550.72  4816.9 1544.41  4899.3 1543.70
  4981.7 1536.11  4994.4 1529.48  4994.9 1528.98  5012.7 1529.48  5014.0 1533.08
  5017.0 1534.28  5093.5 1545.52  5113.7 1547.00  5129.5 1545.14  5172.6 1544.78
#Mann=6,-1,0
  4278.4     0.1       0  4601.1   0.035       0  4740.5    0.07       0
  4899.3   0.035       0  4994.4   0.035       0  5012.7   0.035       0
Bank Sta=4994.4,5012.7
Exp/Cntr=0.3,0.1

Type RM Length L Ch R = 1,21686,595,595,595
BEGIN DESCRIPTION:
Cherry Creek 37.0
END DESCRIPTION:
XS GIS Cut Line= 3
      1975774.99     13871824.99      1976275.00     13872175.00
      1976537.78     13872311.81
#Sta/Elev= 30
  4389.8 1719.52  4424.5 1719.04  4443.9 1714.10  4456.6 1708.84  4476.2 1697.46
  4493.4 1691.11  4515.6 1679.65  4547.3 1666.81  4644.9 1617.72  4698.7 1594.14
  4719.6 1582.78  4749.6 1568.58  4764.6 1560.15  4777.8 1550.48  4786.5 1545.55
  4812.2 1540.63  4823.0 1540.67  4881.2 1534.88  4900.6 1535.13  4911.3 1532.58
  4937.9 1531.60  4953.2 1529.25  4953.7 1528.75  4971.5 1529.25  5039.8 1537.94
  5059.9 1537.76  5119.7 1542.16  5146.4 1540.92  5195.7 1545.84  5296.4 1545.69
#Mann=3,-1,0
  4389.8     0.1       0  4953.2    0.05       0  4971.5     0.1       0
Bank Sta=4953.2,4971.5
Exp/Cntr=0.3,0.1

Type RM Length L Ch R = 1,21091,430,430,430
BEGIN DESCRIPTION:
Cherry Creek 36.0
END DESCRIPTION:
XS GIS Cut Line= 3
      1975774.98     13871874.96      1976200.66     13872615.25
      1977196.35     13873279.73
#Sta/Elev= 30
  4157.2 1717.98  4171.3 1717.44  4195.7 1711.04  4278.7 1668.67  4306.4 1649.57
  4382.5 1610.09  4507.1 1558.20  4544.9 1551.16  4610.9 1545.57  4793.2 1543.41
  4900.1 1539.15  4988.4 1526.32  4988.9 1525.82  5006.7 1526.32  5010.7 1528.27
  5058.4 1529.65  5084.3 1530.69  5110.2 1541.04  5163.3 1540.82  5272.5 1542.56
  5369.8 1550.15  5507.5 1546.42  5712.5 1544.54  5860.3 1548.77  5937.7 1554.58
  6102.7 1563.04  6134.5 1563.24  6166.9 1568.15  6188.6 1566.06  6208.2 1568.36
#Mann=10,-1,0
  4157.2     0.1       0  4900.1    0.07       0  4988.4   0.035       0
  5006.7    0.07       0  5058.4    0.07       0  5163.3     0.1       0
  5507.5   0.035       0  5860.3    0.07       0  5937.7   0.035       0
  6102.7    0.07       0
Bank Sta=4988.4,5006.7
Exp/Cntr=0.3,0.1

Type RM Length L Ch R = 1,20661,554,554,554
BEGIN DESCRIPTION:
Cherry Creek 35.0
END DESCRIPTION:
XS GIS Cut Line= 3
      1975525.02     13872125.04      1975925.00     13872925.00
      1976475.03     13873325.02
#Sta/Elev= 30
  4105.4 1659.22  4126.5 1655.61  4144.8 1644.95  4160.5 1637.83  4185.1 1629.31
  4208.6 1617.73  4285.2 1587.10  4312.5 1579.61  4352.8 1573.05  4432.8 1554.02
  4533.4 1543.95  4630.3 1541.25  4835.3 1538.74  4881.5 1532.50  4897.9 1530.62
  4921.5 1530.80  4953.0 1527.26  4985.1 1526.91  4986.4 1522.83  4986.9 1522.33
  5010.6 1522.83  5011.5 1527.45  5038.1 1528.49  5064.1 1536.73  5076.8 1538.16
  5096.6 1537.49  5107.4 1538.49  5372.3 1534.31  5464.7 1535.43  5679.9 1547.75
#Mann=8,-1,0
  4105.4    0.07       0  4160.5     0.1       0  4630.3    0.07       0
  4881.5     0.1       0  4953.0   0.035       0  4986.4   0.035       0
  5010.6   0.035       0  5096.6    0.07       0
Bank Sta=4986.4,5010.6
Exp/Cntr=0.3,0.1

Type RM Length L Ch R = 1,20107,596,596,596
BEGIN DESCRIPTION:
Cherry Creek 34.0
END DESCRIPTION:
XS GIS Cut Line= 3
      1975374.99     13872874.98      1975525.00     13873275.00
      1976324.96     13873474.99
#Sta/Elev= 30
  4564.3 1571.94  4618.9 1574.65  4651.6 1574.02  4695.8 1569.94  4749.4 1562.27
  4781.4 1559.23  4817.0 1551.53  4843.5 1541.41  4861.0 1533.06  4877.6 1527.72
  4906.4 1525.31  4926.5 1525.71  4952.1 1523.40  4966.1 1524.69  4994.2 1523.52
  4996.7 1523.08  4999.5 1519.08  5000.0 1518.58  5023.7 1519.08  5024.5 1523.84
  5048.7 1528.60  5055.4 1531.53  5067.8 1534.52  5083.3 1536.46  5147.6 1535.02
  5339.9 1535.19  5590.4 1530.60  5612.7 1531.06  5743.8 1543.69  5816.1 1545.01
#Mann=4,-1,0
  4564.3     0.1       0  4861.0    0.07       0  4999.5    0.05       0
  5023.7    0.07       0
Bank Sta=4999.5,5023.7
Exp/Cntr=0.3,0.1

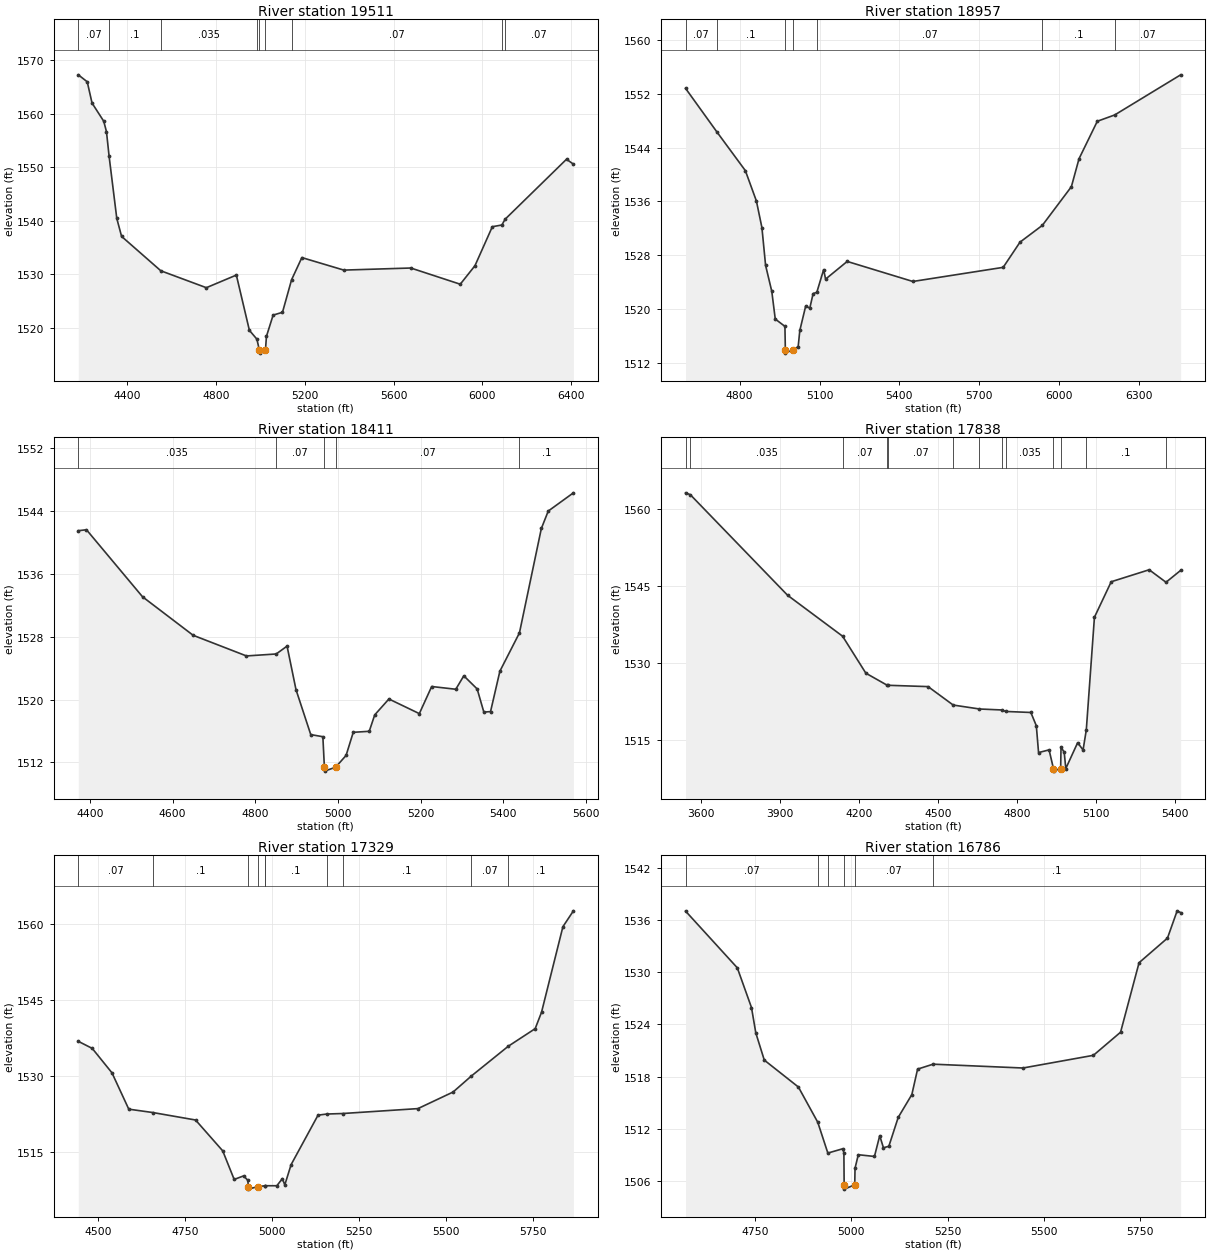
Type RM Length L Ch R = 1,19511,554,554,554
BEGIN DESCRIPTION:
Cherry Creek 33.0
END DESCRIPTION:
XS GIS Cut Line= 3
      1974374.99     13873925.00      1975175.00     13873725.00
      1976575.00     13873625.00
#Sta/Elev= 30
  4181.3 1567.31  4221.5 1566.01  4243.2 1562.03  4295.7 1558.64  4308.1 1556.69
  4320.0 1552.06  4354.5 1540.47  4376.1 1537.11  4552.7 1530.68  4757.6 1527.52
  4892.6 1529.88  4951.3 1519.55  4985.1 1517.90  4996.5 1515.79  4997.0 1515.29
  5023.5 1515.79  5028.0 1518.42  5058.1 1522.40  5100.2 1522.92  5141.1 1529.00
  5187.4 1533.15  5376.2 1530.81  5677.7 1531.20  5900.2 1528.17  5966.4 1531.63
  6044.6 1538.92  6087.5 1539.24  6102.1 1540.32  6378.4 1551.53  6409.5 1550.61
#Mann=9,-1,0
  4181.3    0.07       0  4320.0     0.1       0  4552.7   0.035       0
  4985.1     0.1       0  4996.5    0.05       0  5023.5     0.1       0
  5141.1    0.07       0  6087.5     0.1       0  6102.1    0.07       0
Bank Sta=4996.5,5023.5
Exp/Cntr=0.3,0.1

Type RM Length L Ch R = 1,18957,546,546,546
BEGIN DESCRIPTION:
Cherry Creek 32.0
END DESCRIPTION:
XS GIS Cut Line= 3
      1974974.99     13874375.01      1975325.00     13874175.00
      1976724.96     13873775.01
#Sta/Elev= 30
  4596.9 1552.82  4714.9 1546.32  4821.5 1540.58  4863.0 1536.06  4883.7 1532.10
  4897.5 1526.48  4920.7 1522.63  4933.8 1518.50  4970.1 1517.41  4971.7 1513.93
  4972.2 1513.43  4998.9 1513.93  5019.8 1514.38  5026.0 1516.80  5047.9 1520.41
  5063.5 1520.13  5076.0 1522.29  5089.8 1522.47  5115.4 1525.85  5122.8 1524.44
  5203.9 1527.07  5450.4 1524.09  5789.6 1526.19  5852.8 1529.94  5936.5 1532.43
  6045.7 1538.19  6074.4 1542.35  6143.0 1547.92  6208.3 1548.86  6456.0 1554.83
#Mann=7,-1,0
  4596.9    0.07       0  4714.9     0.1       0  4971.7    0.05       0
  4998.9     0.1       0  5089.8    0.07       0  5936.5     0.1       0
  6208.3    0.07       0
Bank Sta=4971.7,4998.9
Exp/Cntr=0.3,0.1

Type RM Length L Ch R = 1,18411,573,573,573
BEGIN DESCRIPTION:
Cherry Creek 31.0
END DESCRIPTION:
XS GIS Cut Line= 4
      1975275.01     13874625.00      1975725.97     13874415.83
      1975903.61     13874245.04      1976324.97     13874075.01
#Sta/Elev= 30
  4371.8 1541.50  4391.6 1541.62  4527.2 1533.09  4649.6 1528.19  4778.6 1525.56
  4850.6 1525.81  4876.9 1526.81  4898.5 1521.27  4934.2 1515.55  4963.5 1515.28
  4967.2 1511.40  4967.7 1510.90  4994.4 1511.40  5019.7 1512.90  5037.0 1515.84
  5075.7 1515.97  5089.0 1518.06  5123.3 1520.08  5196.9 1518.22  5226.8 1521.67
  5285.1 1521.32  5304.5 1523.03  5336.8 1521.36  5353.0 1518.41  5369.2 1518.48
  5391.8 1523.62  5439.1 1528.49  5492.1 1541.78  5508.8 1544.00  5569.7 1546.32
#Mann=5,-1,0
  4371.8   0.035       0  4850.6    0.07       0  4967.2    0.05       0
  4994.4    0.07       0  5439.1     0.1       0
Bank Sta=4967.2,4994.4
Exp/Cntr=0.3,0.1

Type RM Length L Ch R = 1,17838,509,509,509
BEGIN DESCRIPTION:
Cherry Creek 30.0
END DESCRIPTION:
XS GIS Cut Line= 3
      1974874.97     13874725.00      1976325.00     13874525.00
      1976698.94     13874337.21
#Sta/Elev= 30
  3540.2 1563.16  3558.5 1562.79  3928.2 1543.16  4137.2 1535.17  4225.7 1527.95
  4307.0 1525.59  4308.7 1525.59  4462.2 1525.33  4557.7 1521.73  4657.6 1520.96
  4742.4 1520.77  4757.5 1520.48  4852.9 1520.28  4873.7 1517.69  4882.2 1512.45
  4922.2 1512.98  4938.8 1509.33  4939.3 1508.83  4966.2 1509.33  4967.6 1513.54
  4979.7 1512.51  4985.8 1509.34  5030.8 1514.38  5051.4 1512.96  5063.7 1516.87
  5094.6 1538.87  5158.4 1545.80  5302.7 1548.14  5366.7 1545.70  5422.4 1548.02
#Mann=13,-1,0
  3540.2    0.07       0  3558.5   0.035       0  4137.2    0.07       0
  4307.0   0.035       0  4308.7    0.07       0  4557.7     0.1       0
  4657.6   0.035       0  4742.4     0.1       0  4757.5   0.035       0
  4938.8    0.05       0  4966.2   0.035       0  5063.7     0.1       0
  5366.7    0.07       0
Bank Sta=4938.8,4966.2
Exp/Cntr=0.3,0.1

Type RM Length L Ch R = 1,17329,543,543,543
BEGIN DESCRIPTION:
Cherry Creek 29.0
END DESCRIPTION:
XS GIS Cut Line= 3
      1975474.96     13874875.00      1976025.00     13874875.00
      1976825.04     13875225.02
#Sta/Elev= 30
  4443.5 1536.91  4483.6 1535.51  4540.3 1530.69  4588.6 1523.52  4658.2 1522.85
  4780.6 1521.38  4858.6 1515.30  4891.6 1509.65  4918.6 1510.35  4930.9 1509.48
  4932.2 1508.24  4932.7 1507.74  4959.6 1508.24  4980.2 1508.40  4981.6 1508.41
  5014.3 1508.41  5030.2 1509.82  5037.1 1508.57  5055.3 1512.58  5132.7 1522.34
  5158.1 1522.56  5203.2 1522.66  5419.8 1523.63  5520.8 1526.90  5573.4 1530.06
  5679.6 1535.94  5756.9 1539.41  5775.1 1542.64  5836.6 1559.53  5866.8 1562.66
#Mann=10,-1,0
  4443.5    0.07       0  4658.2     0.1       0  4932.2    0.05       0
  4959.6     0.1       0  4980.2    0.07       0  4981.6     0.1       0
  5158.1    0.07       0  5203.2     0.1       0  5573.4    0.07       0
  5679.6     0.1       0
Bank Sta=4932.2,4959.6
Exp/Cntr=0.3,0.1

Type RM Length L Ch R = 1,16786,585,585,585
BEGIN DESCRIPTION:
Cherry Creek 28.0
END DESCRIPTION:
XS GIS Cut Line= 3
      1975475.02     13874925.03      1975725.00     13875275.00
      1976525.02     13875575.01
#Sta/Elev= 30
  4569.9 1537.04  4704.2 1530.51  4741.0 1525.94  4752.2 1523.02  4774.2 1519.89
  4862.7 1516.79  4912.9 1512.74  4939.1 1509.19  4978.0 1509.69  4980.7 1509.22
  4981.4 1505.54  4981.9 1505.04  5008.9 1505.54  5009.6 1507.44  5018.1 1509.00
  5060.0 1508.80  5073.7 1511.19  5083.3 1509.80  5097.3 1509.97  5121.7 1513.30
  5157.0 1515.92  5171.9 1518.85  5212.1 1519.42  5445.3 1518.98  5628.0 1520.44
  5698.5 1523.10  5746.5 1531.10  5820.2 1533.93  5845.3 1537.07  5854.4 1536.87
#Mann=6,-1,0
  4569.9    0.07       0  4912.9     0.1       0  4939.1    0.07       0
  4981.4    0.05       0  5008.9    0.07       0  5212.1     0.1       0
Bank Sta=4981.4,5008.9
Exp/Cntr=0.3,0.1

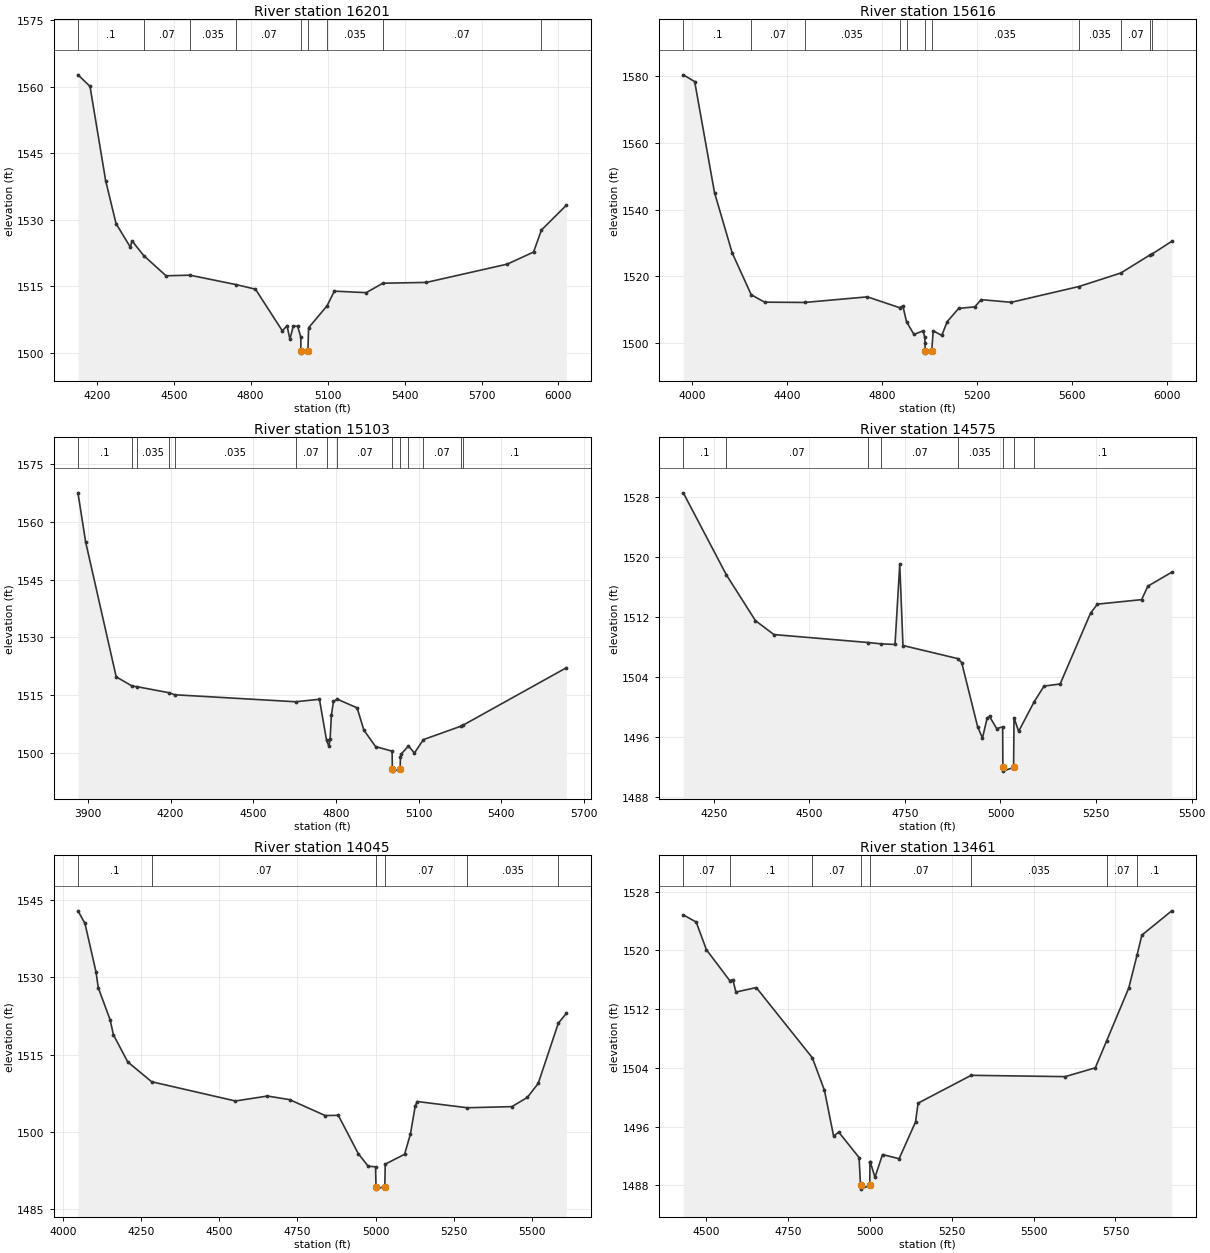
Type RM Length L Ch R = 1,16201,585,585,585
BEGIN DESCRIPTION:
Cherry Creek 27.0
END DESCRIPTION:
XS GIS Cut Line= 3
      1974575.02     13875375.01      1975375.00     13875725.00
      1976175.02     13876375.02
#Sta/Elev= 30
  4126.8 1562.70  4173.7 1560.11  4234.8 1538.82  4275.2 1529.15  4330.9 1523.85
  4337.5 1525.25  4383.1 1521.93  4470.2 1517.38  4563.3 1517.51  4744.8 1515.37
  4818.8 1514.35  4923.5 1504.96  4941.8 1506.11  4953.1 1503.05  4966.2 1506.05
  4983.3 1505.98  4995.6 1503.46  4995.7 1500.43  4996.2 1499.93  5023.2 1500.43
  5025.8 1505.64  5097.6 1510.58  5126.3 1513.91  5250.4 1513.57  5315.6 1515.70
  5485.0 1515.88  5800.7 1520.01  5902.8 1522.73  5933.5 1527.69  6030.8 1533.30
#Mann=9,-1,0
  4126.8     0.1       0  4383.1    0.07       0  4563.3   0.035       0
  4744.8    0.07       0  4995.7    0.05       0  5023.2    0.07       0
  5097.6   0.035       0  5315.6    0.07       0  5933.5     0.1       0
Bank Sta=4995.7,5023.2
Exp/Cntr=0.3,0.1

Type RM Length L Ch R = 1,15616,513,513,513
BEGIN DESCRIPTION:
Cherry Creek 26.0
END DESCRIPTION:
XS GIS Cut Line= 3
      1974225.00     13875525.00      1975025.00     13876175.00
      1975775.00     13876875.00
#Sta/Elev= 30
  3964.3 1580.39  4012.2 1578.36  4095.7 1545.09  4170.0 1527.04  4250.3 1514.47
  4306.5 1512.25  4475.3 1512.16  4739.4 1513.84  4874.7 1510.60  4888.7 1511.12
  4904.3 1506.37  4935.6 1502.56  4974.0 1503.66  4980.9 1501.73  4982.5 1499.92
  4982.6 1497.47  4983.1 1496.97  5010.3 1497.47  5016.5 1503.68  5052.6 1502.27
  5076.0 1506.45  5123.7 1510.37  5191.9 1510.84  5218.1 1513.00  5345.3 1512.21
  5630.5 1516.94  5806.4 1520.98  5929.0 1526.38  5937.3 1526.64  6021.0 1530.48
#Mann=11,-1,0
  3964.3     0.1       0  4250.3    0.07       0  4475.3   0.035       0
  4874.7    0.07       0  4904.3   0.035       0  4982.6    0.05       0
  5010.3   0.035       0  5630.5   0.035       0  5806.4    0.07       0
  5929.0   0.035       0  5937.3     0.1       0
Bank Sta=4982.6,5010.3
Exp/Cntr=0.3,0.1

Type RM Length L Ch R = 1,15103,528,528,528
BEGIN DESCRIPTION:
Cherry Creek 25.0
END DESCRIPTION:
XS GIS Cut Line= 3
      1974024.97     13875824.97      1974825.00     13876625.00
      1975324.98     13877024.98
#Sta/Elev= 30
  3864.2 1567.54  3892.0 1554.79  4002.9 1519.72  4060.8 1517.31  4079.2 1517.15
  4195.9 1515.56  4214.9 1515.06  4653.8 1513.24  4740.1 1513.88  4766.0 1503.22
  4774.5 1501.63  4778.8 1503.53  4783.5 1509.77  4791.0 1513.35  4805.0 1513.91
  4876.8 1511.65  4901.3 1505.87  4943.7 1501.59  5003.7 1500.40  5004.7 1495.71
  5005.2 1495.21  5032.7 1495.71  5034.0 1498.88  5037.7 1499.72  5062.9 1501.74
  5084.8 1499.93  5117.2 1503.40  5251.8 1506.85  5261.3 1507.16  5635.9 1522.08
#Mann=14,-1,0
  3864.2     0.1       0  4060.8    0.07       0  4079.2   0.035       0
  4195.9    0.07       0  4214.9   0.035       0  4653.8    0.07       0
  4766.0   0.035       0  4805.0    0.07       0  5004.7    0.05       0
  5032.7    0.07       0  5062.9   0.035       0  5117.2    0.07       0
  5251.8   0.035       0  5261.3     0.1       0
Bank Sta=5004.7,5032.7
Exp/Cntr=0.3,0.1

Type RM Length L Ch R = 1,14575,530,530,530
BEGIN DESCRIPTION:
Cherry Creek 24.0
END DESCRIPTION:
XS GIS Cut Line= 3
      1973924.99     13876925.00      1974725.00     13877125.00
      1975175.00     13877075.00
#Sta/Elev= 30
  4170.5 1528.57  4283.1 1517.63  4359.1 1511.52  4407.4 1509.66  4653.6 1508.60
  4687.9 1508.42  4724.2 1508.34  4736.6 1519.03  4745.0 1508.20  4887.8 1506.46
  4898.5 1505.93  4940.5 1497.32  4952.9 1495.85  4965.2 1498.54  4971.4 1498.73
  4990.0 1497.12  5005.7 1497.34  5006.3 1491.94  5006.8 1491.44  5034.3 1491.94
  5035.4 1498.57  5047.5 1496.75  5088.2 1500.70  5113.9 1502.78  5156.1 1503.07
  5235.7 1512.53  5253.6 1513.72  5369.1 1514.32  5385.5 1516.12  5447.9 1517.98
#Mann=8,-1,0
  4170.5     0.1       0  4283.1    0.07       0  4653.6   0.035       0
  4687.9    0.07       0  4887.8   0.035       0  5006.3   0.035       0
  5034.3   0.035       0  5088.2     0.1       0
Bank Sta=5006.3,5034.3
Exp/Cntr=0.3,0.1

Type RM Length L Ch R = 1,14045,584,584,584
BEGIN DESCRIPTION:
Cherry Creek 23.0
END DESCRIPTION:
XS GIS Cut Line= 3
      1973825.01     13877125.01      1974625.00     13877625.00
      1975225.05     13877474.99
#Sta/Elev= 30
  4048.5 1542.86  4070.9 1540.42  4106.3 1530.99  4113.4 1527.97  4151.1 1521.78
  4162.0 1518.83  4207.7 1513.58  4284.1 1509.74  4552.0 1506.01  4654.6 1506.97
  4725.4 1506.27  4839.0 1503.19  4881.0 1503.23  4944.7 1495.83  4976.6 1493.37
  5000.1 1493.26  5001.6 1489.43  5002.1 1488.93  5029.7 1489.43  5031.1 1493.77
  5092.9 1495.68  5111.5 1499.56  5126.9 1504.99  5133.1 1505.91  5293.4 1504.70
  5436.3 1504.92  5485.6 1506.71  5520.2 1509.40  5584.7 1521.10  5610.4 1523.00
#Mann=6,-1,0
  4048.5     0.1       0  4284.1    0.07       0  5001.6    0.05       0
  5029.7    0.07       0  5293.4   0.035       0  5584.7     0.1       0
Bank Sta=5001.6,5029.7
Exp/Cntr=0.3,0.1

Type RM Length L Ch R = 1,13461,571,571,571
BEGIN DESCRIPTION:
Cherry Creek 22.0
END DESCRIPTION:
XS GIS Cut Line= 3
      1974174.99     13878325.00      1974725.00     13878175.00
      1975324.97     13877475.04
#Sta/Elev= 30
  4429.9 1524.84  4469.3 1523.86  4500.4 1520.10  4571.7 1515.89  4581.2 1516.02
  4590.6 1514.33  4652.8 1514.94  4824.0 1505.38  4861.1 1500.94  4889.1 1494.70
  4904.6 1495.26  4966.8 1491.79  4971.3 1487.99  4971.8 1487.49  4999.6 1487.99
  5000.0 1491.13  5000.9 1491.20  5015.4 1489.11  5038.4 1492.20  5089.1 1491.63
  5139.2 1496.63  5147.1 1499.20  5309.3 1502.99  5596.2 1502.81  5688.4 1504.01
  5723.1 1507.69  5790.5 1514.86  5815.7 1519.31  5830.6 1522.08  5921.9 1525.39
#Mann=8,-1,0
  4429.9    0.07       0  4571.7     0.1       0  4824.0    0.07       0
  4971.3    0.05       0  4999.6    0.07       0  5309.3   0.035       0
  5723.1    0.07       0  5815.7     0.1       0
Bank Sta=4971.3,4999.6
Exp/Cntr=0.3,0.1

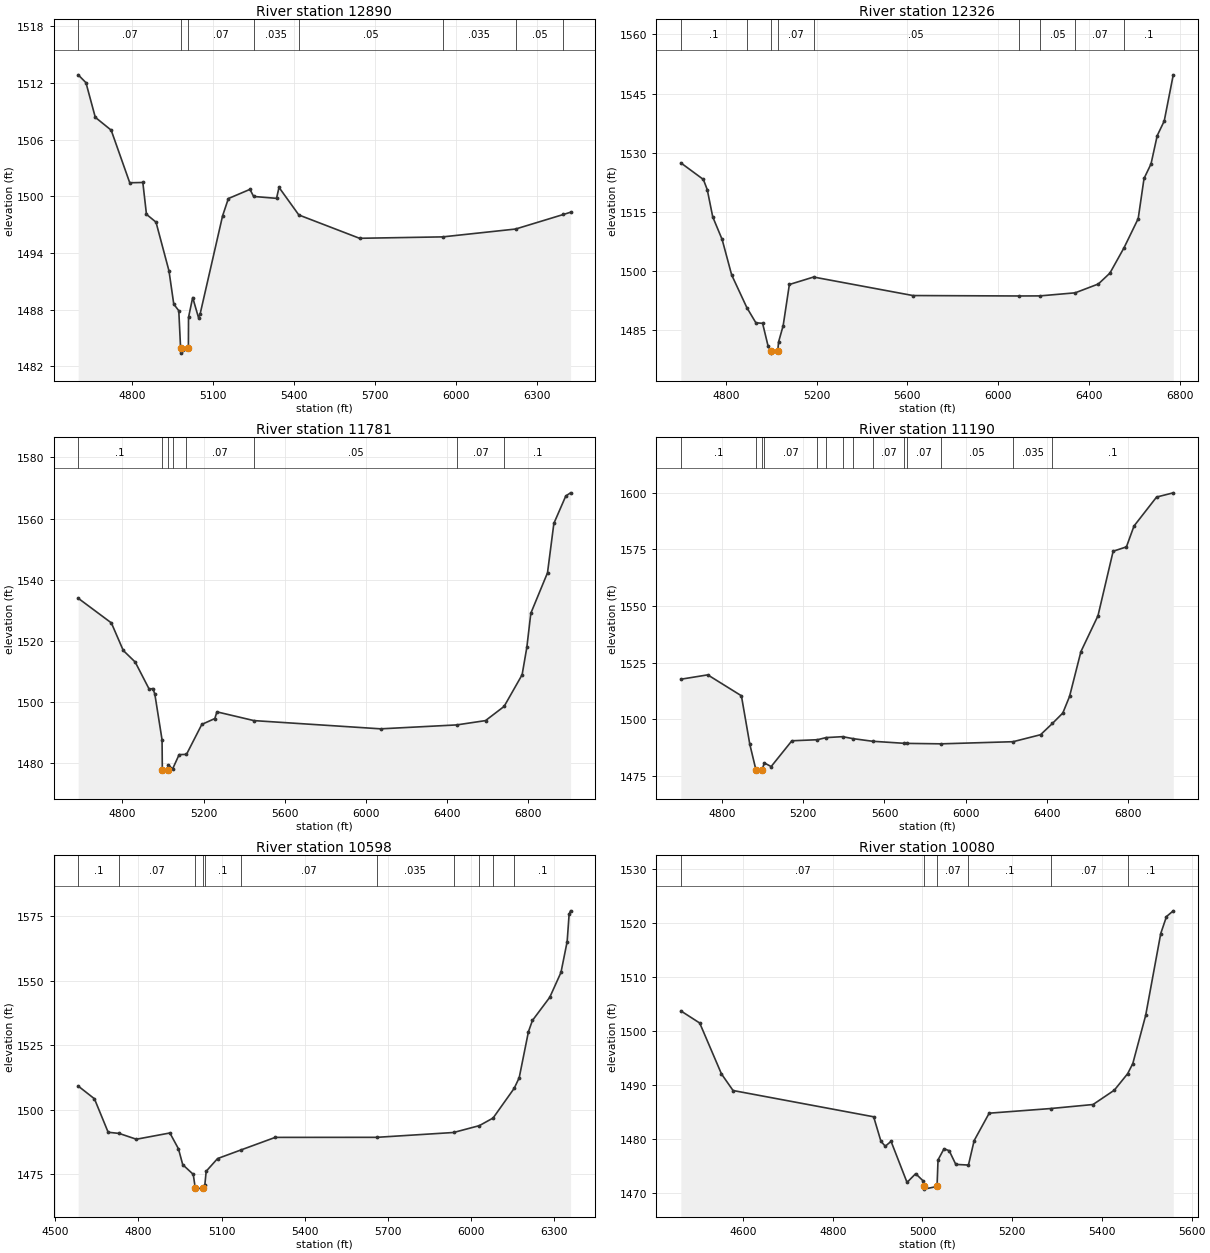
Type RM Length L Ch R = 1,12890,564,564,564
BEGIN DESCRIPTION:
Cherry Creek 21.0
END DESCRIPTION:
XS GIS Cut Line= 3
      1974575.01     13878875.00      1974925.00     13878675.00
      1976310.56     13878372.99
#Sta/Elev= 30
  4601.5 1512.86  4630.3 1512.03  4664.9 1508.36  4723.6 1507.00  4792.3 1501.43
  4840.7 1501.46  4854.1 1498.09  4889.4 1497.26  4937.4 1492.10  4955.1 1488.58
  4973.7 1487.88  4980.4 1483.89  4980.9 1483.39  5009.2 1483.89  5009.7 1487.18
  5025.1 1489.28  5046.6 1487.15  5052.7 1487.55  5135.6 1497.92  5157.1 1499.76
  5236.9 1500.73  5250.5 1499.98  5335.2 1499.78  5344.4 1500.94  5417.7 1498.02
  5642.2 1495.55  5950.0 1495.70  6219.2 1496.53  6396.0 1498.07  6422.7 1498.31
#Mann=8,-1,0
  4601.5    0.07       0  4980.4    0.05       0  5009.2    0.07       0
  5250.5   0.035       0  5417.7    0.05       0  5950.0   0.035       0
  6219.2    0.05       0  6396.0    0.07       0
Bank Sta=4980.4,5009.2
Exp/Cntr=0.3,0.1

Type RM Length L Ch R = 1,12326,545,545,545
BEGIN DESCRIPTION:
Cherry Creek 20.0
END DESCRIPTION:
XS GIS Cut Line= 3
      1974775.01     13879375.00      1975125.00     13879175.00
      1976675.03     13878324.99
#Sta/Elev= 30
  4601.5 1527.42  4700.6 1523.23  4717.8 1520.65  4742.0 1513.74  4783.5 1508.00
  4825.5 1499.01  4892.5 1490.72  4932.1 1486.89  4961.9 1486.74  4986.0 1480.99
  4999.8 1479.69  5000.3 1479.19  5028.7 1479.69  5032.3 1482.02  5052.5 1486.15
  5079.9 1496.59  5186.7 1498.48  5624.6 1493.79  6092.4 1493.68  6184.1 1493.70
  6340.0 1494.48  6442.1 1496.72  6493.0 1499.47  6555.4 1505.91  6617.8 1513.29
  6643.5 1523.47  6674.3 1527.16  6701.7 1534.34  6732.5 1538.03  6772.4 1549.75
#Mann=9,-1,0
  4601.5     0.1       0  4892.5    0.07       0  4999.8    0.05       0
  5028.7    0.07       0  5186.7    0.05       0  6092.4   0.035       0
  6184.1    0.05       0  6340.0    0.07       0  6555.4     0.1       0
Bank Sta=4999.8,5028.7
Exp/Cntr=0.3,0.1

Type RM Length L Ch R = 1,11781,591,591,591
BEGIN DESCRIPTION:
Cherry Creek 19.0
END DESCRIPTION:
XS GIS Cut Line= 3
      1974875.03     13879874.98      1975225.00     13879675.00
      1976775.02     13878374.98
#Sta/Elev= 30
  4582.0 1533.98  4745.5 1525.91  4804.3 1516.89  4863.0 1513.11  4932.0 1504.23
  4950.1 1504.45  4959.7 1502.65  4995.4 1487.67  4996.7 1477.94  4997.2 1477.44
  5025.6 1477.94  5026.9 1479.50  5047.1 1478.12  5079.5 1482.84  5115.7 1482.92
  5191.3 1492.72  5255.3 1494.63  5265.7 1496.82  5448.2 1493.96  6072.3 1491.27
  6447.0 1492.55  6589.1 1493.96  6680.7 1498.60  6769.4 1508.95  6792.7 1517.93
  6812.3 1529.06  6894.5 1542.29  6925.9 1558.45  6984.6 1567.41  7008.1 1568.44
#Mann=8,-1,0
  4582.0     0.1       0  4996.7    0.05       0  5025.6     0.1       0
  5047.1     0.1       0  5115.7    0.07       0  5448.2    0.05       0
  6447.0    0.07       0  6680.7     0.1       0
Bank Sta=4996.7,5025.6
Exp/Cntr=0.3,0.1

Type RM Length L Ch R = 1,11190,592,592,592
BEGIN DESCRIPTION:
Cherry Creek 18.0
END DESCRIPTION:
XS GIS Cut Line= 3
      1975325.01     13880224.99      1975675.00     13880025.00
      1977225.01     13878724.99
#Sta/Elev= 30
  4596.9 1517.62  4729.3 1519.55  4895.2 1510.30  4936.7 1488.80  4967.0 1477.48
  4967.5 1476.98  4995.9 1477.48  5008.6 1480.57  5041.8 1479.00  5143.9 1490.40
  5270.0 1490.87  5312.6 1491.81  5393.7 1492.22  5444.8 1491.35  5541.2 1490.19
  5697.0 1489.28  5709.0 1489.25  5879.5 1489.05  6233.5 1489.99  6369.1 1493.08
  6427.6 1498.07  6478.8 1502.67  6512.0 1510.02  6568.1 1529.86  6652.1 1545.70
  6726.8 1574.21  6792.2 1576.15  6829.5 1585.36  6940.8 1598.18  7023.0 1600.05
#Mann=14,-1,0
  4596.9     0.1       0  4967.0    0.05       0  4995.9     0.1       0
  5008.6    0.07       0  5270.0    0.05       0  5312.6    0.07       0
  5393.7    0.05       0  5444.8   0.035       0  5541.2    0.07       0
  5697.0   0.035       0  5709.0    0.07       0  5879.5    0.05       0
  6233.5   0.035       0  6427.6     0.1       0
Bank Sta=4967,4995.9
Exp/Cntr=0.3,0.1

Type RM Length L Ch R = 1,10598,518,518,518
BEGIN DESCRIPTION:
Cherry Creek 17.0
END DESCRIPTION:
XS GIS Cut Line= 3
      1975725.02     13880474.99      1976125.00     13880375.00
      1977238.26     13879586.51
#Sta/Elev= 30
  4582.7 1509.15  4641.4 1504.20  4690.9 1491.20  4730.5 1490.75  4792.7 1488.49
  4913.6 1490.92  4944.5 1484.79  4960.0 1478.61  4997.9 1474.86  5005.1 1469.62
  5005.6 1469.12  5034.0 1469.62  5039.8 1470.85  5044.6 1476.06  5085.7 1480.99
  5171.3 1484.38  5293.7 1489.21  5660.2 1489.23  5937.2 1491.11  6030.1 1493.77
  6079.6 1496.72  6155.9 1508.27  6173.9 1512.38  6207.2 1530.24  6221.6 1534.60
  6284.1 1543.59  6324.6 1553.25  6346.9 1565.22  6354.0 1575.86  6359.2 1577.17
#Mann=11,-1,0
  4582.7     0.1       0  4730.5    0.07       0  5005.1    0.05       0
  5034.0    0.07       0  5039.8     0.1       0  5171.3    0.07       0
  5660.2   0.035       0  5937.2    0.07       0  6030.1   0.035       0
  6079.6    0.07       0  6155.9     0.1       0
Bank Sta=5005.1,5034
Exp/Cntr=0.3,0.1

Type RM Length L Ch R = 1,10080,559,559,559
BEGIN DESCRIPTION:
Cherry Creek 16.0
END DESCRIPTION:
XS GIS Cut Line= 3
      1976025.00     13880825.00      1976525.00     13880625.00
      1977024.97     13880375.01
#Sta/Elev= 30
  4461.5 1503.73  4503.5 1501.48  4552.0 1492.03  4577.8 1488.95  4891.2 1484.07
  4907.4 1479.54  4917.1 1478.60  4930.0 1479.51  4965.6 1471.89  4984.9 1473.51
  5001.1 1472.20  5003.3 1471.14  5003.8 1470.64  5032.5 1471.14  5034.7 1476.07
  5048.1 1478.14  5059.6 1477.77  5074.3 1475.23  5102.5 1475.11  5115.2 1479.65
  5148.7 1484.74  5285.4 1485.60  5380.2 1486.35  5427.6 1489.01  5457.3 1492.07
  5468.8 1493.95  5497.5 1502.90  5531.1 1518.10  5543.9 1521.25  5559.0 1522.31
#Mann=6,-1,0
  4461.5    0.07       0  5003.3    0.05       0  5032.5    0.07       0
  5102.5     0.1       0  5285.4    0.07       0  5457.3     0.1       0
Bank Sta=5003.3,5032.5
Exp/Cntr=0.3,0.1

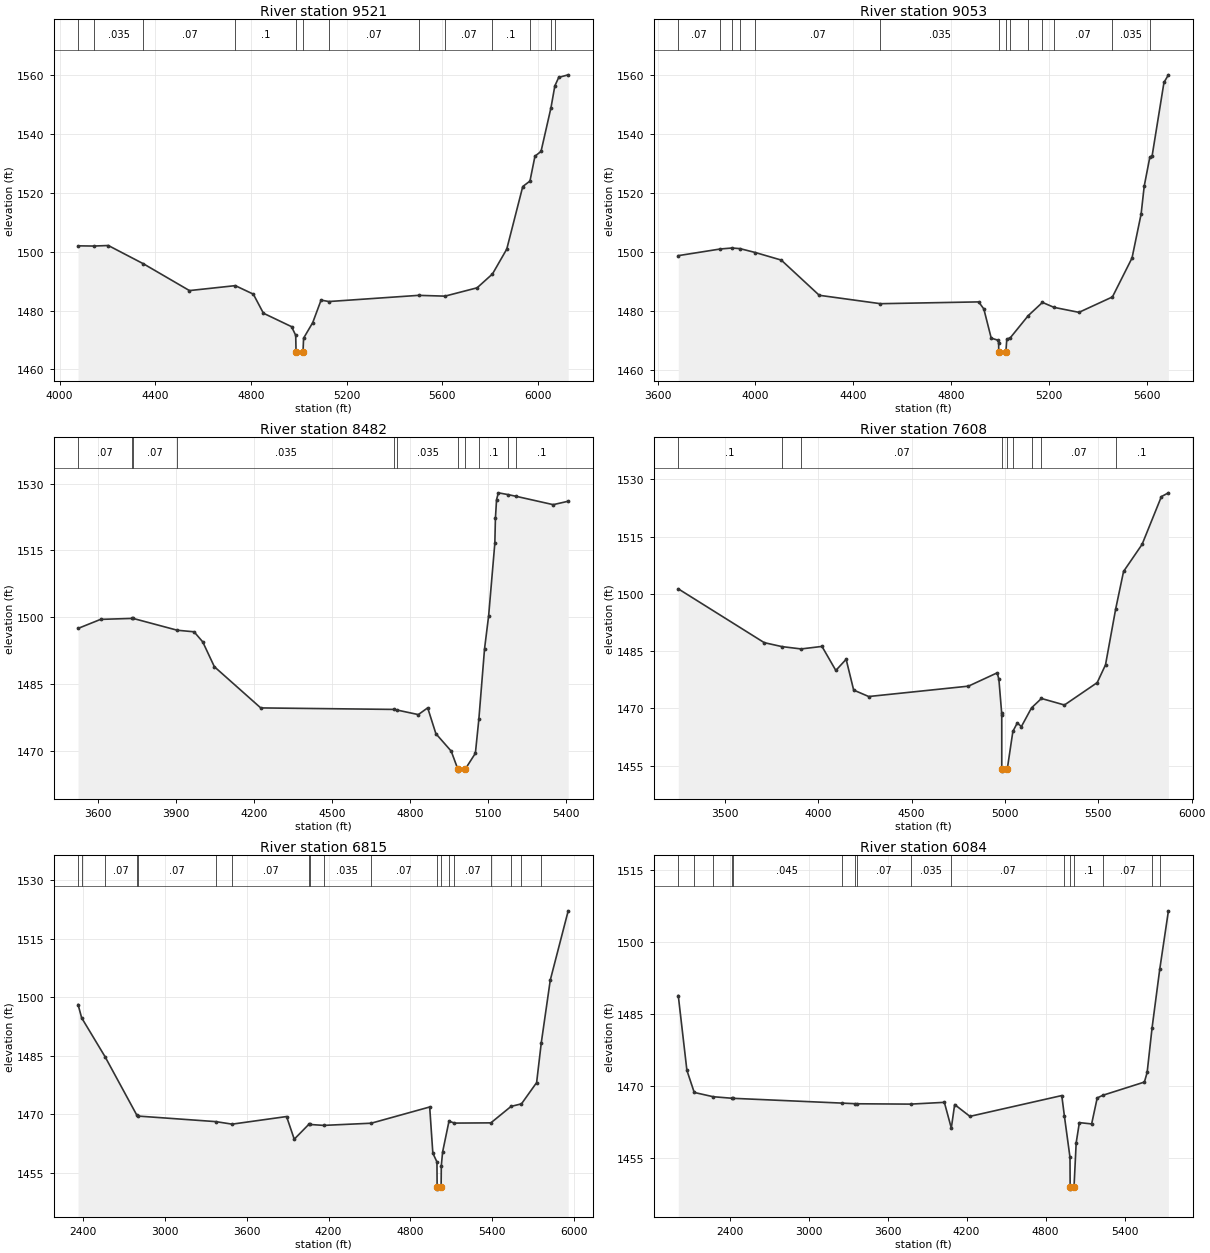
Type RM Length L Ch R = 1,9521,468,468,468
BEGIN DESCRIPTION:
Cherry Creek 15.0
END DESCRIPTION:
XS GIS Cut Line= 3
      1975907.49     13881106.78      1976825.00     13881075.00
      1977624.98     13880275.02
#Sta/Elev= 30
  4076.9 1501.98  4142.1 1501.91  4203.5 1502.09  4350.2 1495.88  4542.7 1486.77
  4734.4 1488.45  4809.8 1485.56  4851.9 1479.08  4969.5 1474.51  4987.0 1471.56
  4988.4 1466.01  4988.9 1465.51  5017.6 1466.01  5019.9 1470.59  5058.1 1475.88
  5093.0 1483.52  5126.2 1483.05  5500.6 1485.15  5611.0 1484.88  5745.4 1487.71
  5809.7 1492.42  5869.4 1500.87  5936.3 1522.14  5966.4 1524.00  5987.3 1532.45
  6012.7 1534.08  6054.4 1548.97  6070.4 1556.33  6086.7 1559.24  6126.3 1560.11
#Mann=13,-1,0
  4076.9    0.07       0  4142.1   0.035       0  4350.2    0.07       0
  4734.4     0.1       0  4988.4    0.05       0  5017.6     0.1       0
  5126.2    0.07       0  5500.6   0.035       0  5611.0    0.07       0
  5809.7     0.1       0  5966.4    0.07       0  6054.4     0.1       0
  6070.4    0.07       0
Bank Sta=4988.4,5017.6
Exp/Cntr=0.3,0.1

Type RM Length L Ch R = 1,9053,571,571,571
BEGIN DESCRIPTION:
Cherry Creek 14.0
END DESCRIPTION:
XS GIS Cut Line= 4
      1975756.31     13881184.07      1976919.88     13881491.24
      1977143.66     13881461.09      1977674.99     13881675.00
#Sta/Elev= 30
  3684.8 1498.77  3856.6 1501.03  3904.1 1501.36  3936.9 1501.15  3999.6 1499.83
  4105.4 1497.27  4260.6 1485.34  4510.7 1482.49  4911.6 1483.10  4932.8 1480.72
  4963.0 1470.83  4990.5 1470.12  4993.3 1469.26  4993.8 1466.24  4994.3 1465.74
  5023.0 1466.24  5026.6 1470.43  5041.7 1471.02  5114.4 1478.46  5172.3 1482.93
  5219.3 1481.25  5321.4 1479.56  5458.1 1484.78  5538.1 1497.97  5575.3 1512.89
  5587.9 1522.31  5610.9 1532.16  5620.2 1532.57  5668.6 1557.46  5686.8 1560.04
#Mann=14,-1,0
  3684.8    0.07       0  3856.6   0.035       0  3904.1    0.07       0
  3936.9   0.035       0  3999.6    0.07       0  4510.7   0.035       0
  4993.8   0.035       0  5023.0   0.035       0  5041.7     0.1       0
  5114.4    0.07       0  5172.3     0.1       0  5219.3    0.07       0
  5458.1   0.035       0  5610.9    0.07       0
Bank Sta=4993.8,5023
Exp/Cntr=0.3,0.1

Type RM Length L Ch R = 1,8482,874,874,874
BEGIN DESCRIPTION:
Cherry Creek 13.0
END DESCRIPTION:
XS GIS Cut Line= 3
      1975739.97     13881334.81      1977075.00     13881975.00
      1977424.99     13882175.00
#Sta/Elev= 30
  3523.7 1497.45  3610.3 1499.48  3730.1 1499.70  3734.5 1499.71  3905.2 1497.04
  3969.6 1496.69  4002.8 1494.43  4047.6 1488.84  4225.8 1479.58  4739.0 1479.24
  4750.6 1479.09  4831.4 1478.08  4867.4 1479.59  4898.9 1473.79  4957.7 1469.87
  4983.0 1465.87  4983.5 1465.37  5012.3 1465.87  5050.7 1469.39  5064.0 1477.02
  5085.9 1492.86  5101.7 1500.32  5125.5 1516.63  5127.7 1522.19  5132.1 1526.42
  5139.1 1527.93  5175.5 1527.54  5205.4 1527.17  5349.8 1525.27  5407.4 1526.04
#Mann=11,-1,0
  3523.7    0.07       0  3730.1   0.035       0  3734.5    0.07       0
  3905.2   0.035       0  4739.0    0.07       0  4750.6   0.035       0
  4983.0    0.05       0  5012.3   0.035       0  5064.0     0.1       0
  5175.5    0.07       0  5205.4     0.1       0
Bank Sta=4983,5012.3
Exp/Cntr=0.3,0.1

Type RM Length L Ch R = 1,7608,793,793,793
BEGIN DESCRIPTION:
Cherry Creek 12.0
END DESCRIPTION:
XS GIS Cut Line= 4
      1975151.65     13881472.47      1976279.38     13882542.05
      1976768.69     13882583.53      1977224.96     13882225.03
#Sta/Elev= 30
  3249.9 1501.32  3710.4 1487.22  3805.4 1486.18  3908.0 1485.57  4019.7 1486.23
  4093.9 1479.93  4149.1 1482.86  4189.4 1474.79  4270.1 1473.10  4804.2 1475.82
  4958.4 1479.31  4967.4 1477.58  4982.4 1468.68  4982.7 1468.23  4982.8 1454.05
  4983.3 1453.55  5012.1 1454.05  5042.3 1463.97  5065.9 1466.17  5087.8 1465.22
  5142.2 1470.13  5195.2 1472.59  5318.5 1470.88  5494.0 1476.74  5538.5 1481.41
  5593.1 1496.08  5635.2 1505.88  5734.4 1512.97  5837.8 1525.49  5875.5 1526.48
#Mann=9,-1,0
  3249.9     0.1       0  3805.4   0.035       0  3908.0    0.07       0
  4982.8    0.05       0  5012.1    0.07       0  5042.3   0.035       0
  5142.2     0.1       0  5195.2    0.07       0  5593.1     0.1       0
Bank Sta=4982.8,5012.1
Exp/Cntr=0.3,0.1

Type RM Length L Ch R = 1,6815,731,731,731
BEGIN DESCRIPTION:
Cherry Creek 11.0
END DESCRIPTION:
XS GIS Cut Line= 4
      1975089.61     13884678.71      1976262.49     13884483.16
      1976875.00     13883175.00      1977236.81     13882282.59
#Sta/Elev= 30
  2362.2 1498.15  2388.7 1494.74  2560.5 1484.77  2793.7 1469.78  2802.8 1469.56
  3371.8 1468.14  3492.8 1467.49  3892.3 1469.44  3948.6 1463.63  4055.2 1467.43
  4066.3 1467.40  4164.1 1467.17  4513.3 1467.73  4942.4 1471.89  4965.5 1460.05
  4995.7 1457.79  4996.9 1451.33  4997.4 1450.83  5026.2 1451.33  5027.7 1456.88
  5037.4 1460.39  5084.0 1468.25  5124.4 1467.76  5391.3 1467.82  5539.6 1472.04
  5616.0 1472.70  5727.0 1478.14  5761.3 1488.37  5827.3 1504.44  5958.7 1522.18
#Mann=19,-1,0
  2362.2    0.07       0  2388.7   0.035       0  2560.5    0.07       0
  2793.7   0.035       0  2802.8    0.07       0  3371.8   0.045       0
  3492.8    0.07       0  4055.2   0.035       0  4066.3    0.07       0
  4164.1   0.035       0  4513.3    0.07       0  4996.9    0.05       0
  5026.2    0.07       0  5084.0     0.1       0  5124.4    0.07       0
  5391.3   0.035       0  5539.6    0.07       0  5616.0   0.035       0
  5761.3     0.1       0
Bank Sta=4996.9,5026.2
Exp/Cntr=0.3,0.1

Type RM Length L Ch R = 1,6084,1007,1007,1007
BEGIN DESCRIPTION:
Cherry Creek 10.0
END DESCRIPTION:
XS GIS Cut Line= 4
      1975406.57     13885117.08      1976921.17     13884507.09
      1977565.87     13883304.22      1977925.02     13882674.97
#Sta/Elev= 30
  2010.5 1488.87  2076.0 1473.31  2131.7 1468.71  2275.0 1467.82  2417.4 1467.50
  2423.9 1467.49  3253.4 1466.49  3350.5 1466.37  3365.6 1466.35  3776.1 1466.28
  4031.1 1466.65  4083.9 1461.30  4109.3 1466.19  4225.1 1463.73  4922.8 1468.06
  4942.8 1463.76  4985.1 1455.21  4986.4 1449.09  4986.9 1448.59  5015.8 1449.09
  5032.1 1458.22  5056.3 1462.43  5149.5 1462.16  5191.9 1467.57  5234.7 1468.12
  5550.2 1470.87  5571.0 1472.87  5608.5 1482.17  5666.7 1494.34  5732.6 1506.50
#Mann=16,-1,0
  2010.5    0.07       0  2131.7   0.035       0  2275.0   0.045       0
  2417.4    0.07       0  2423.9   0.045       0  3253.4    0.07       0
  3350.5   0.045       0  3365.6    0.07       0  3776.1   0.035       0
  4083.9    0.07       0  4942.8     0.1       0  4986.4    0.05       0
  5015.8     0.1       0  5234.7    0.07       0  5608.5   0.035       0
  5666.7     0.1       0
Bank Sta=4986.4,5015.8
Exp/Cntr=0.3,0.1