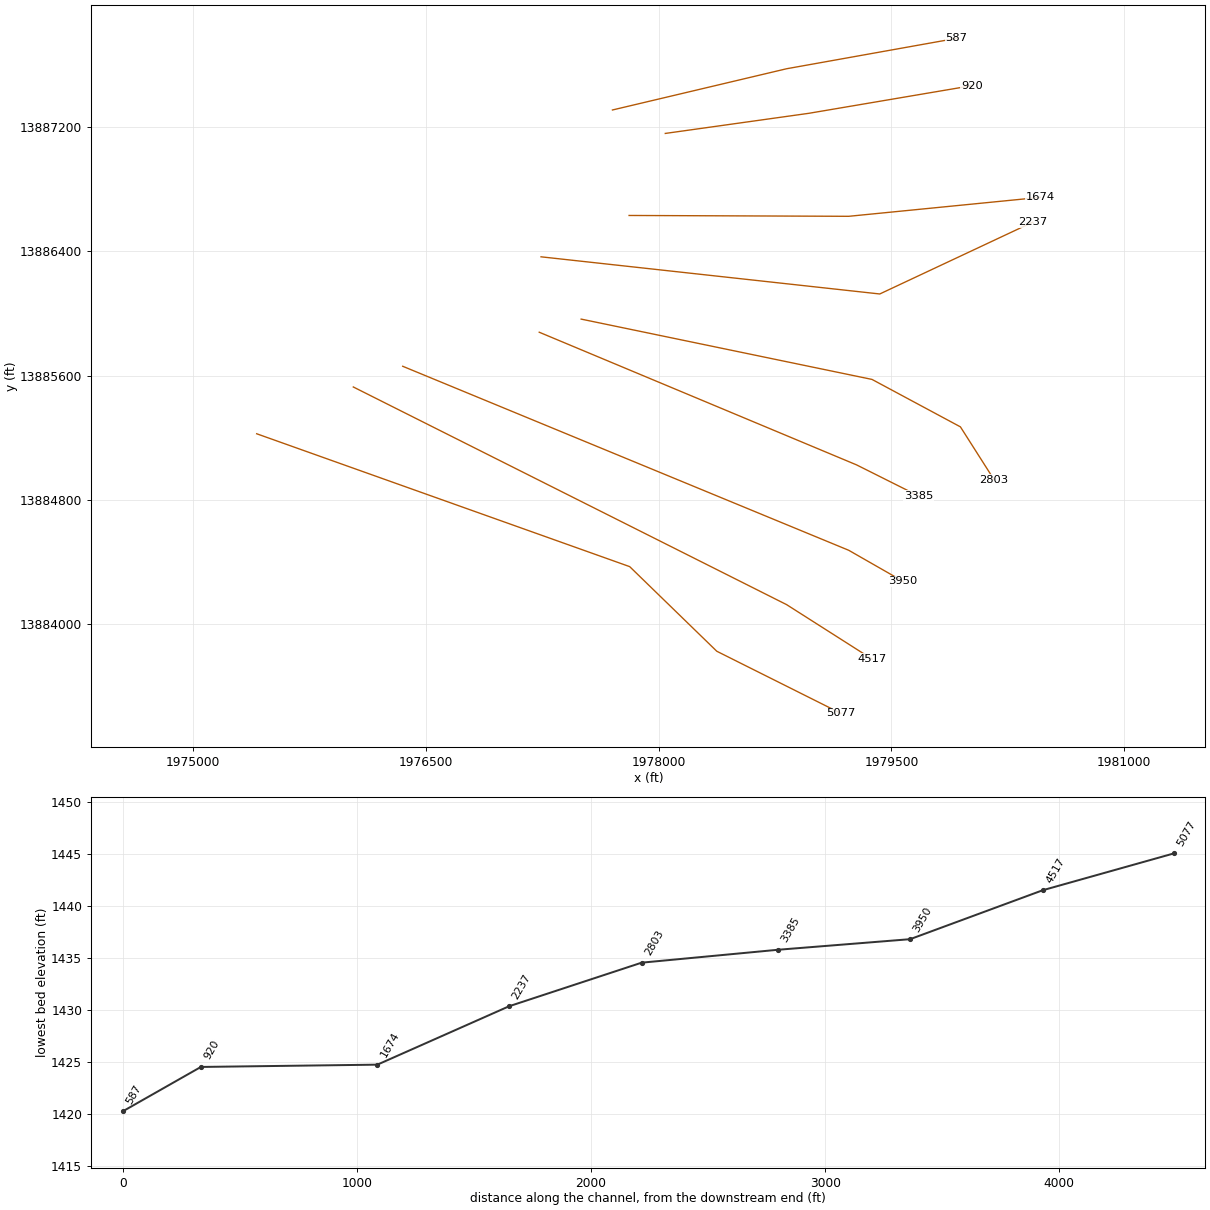
HEC-RAS study Cherry Creek.prj: Cherry Creek Base Level Engineering

--- Cherry Creek.g01 (geometry) --- (continued)

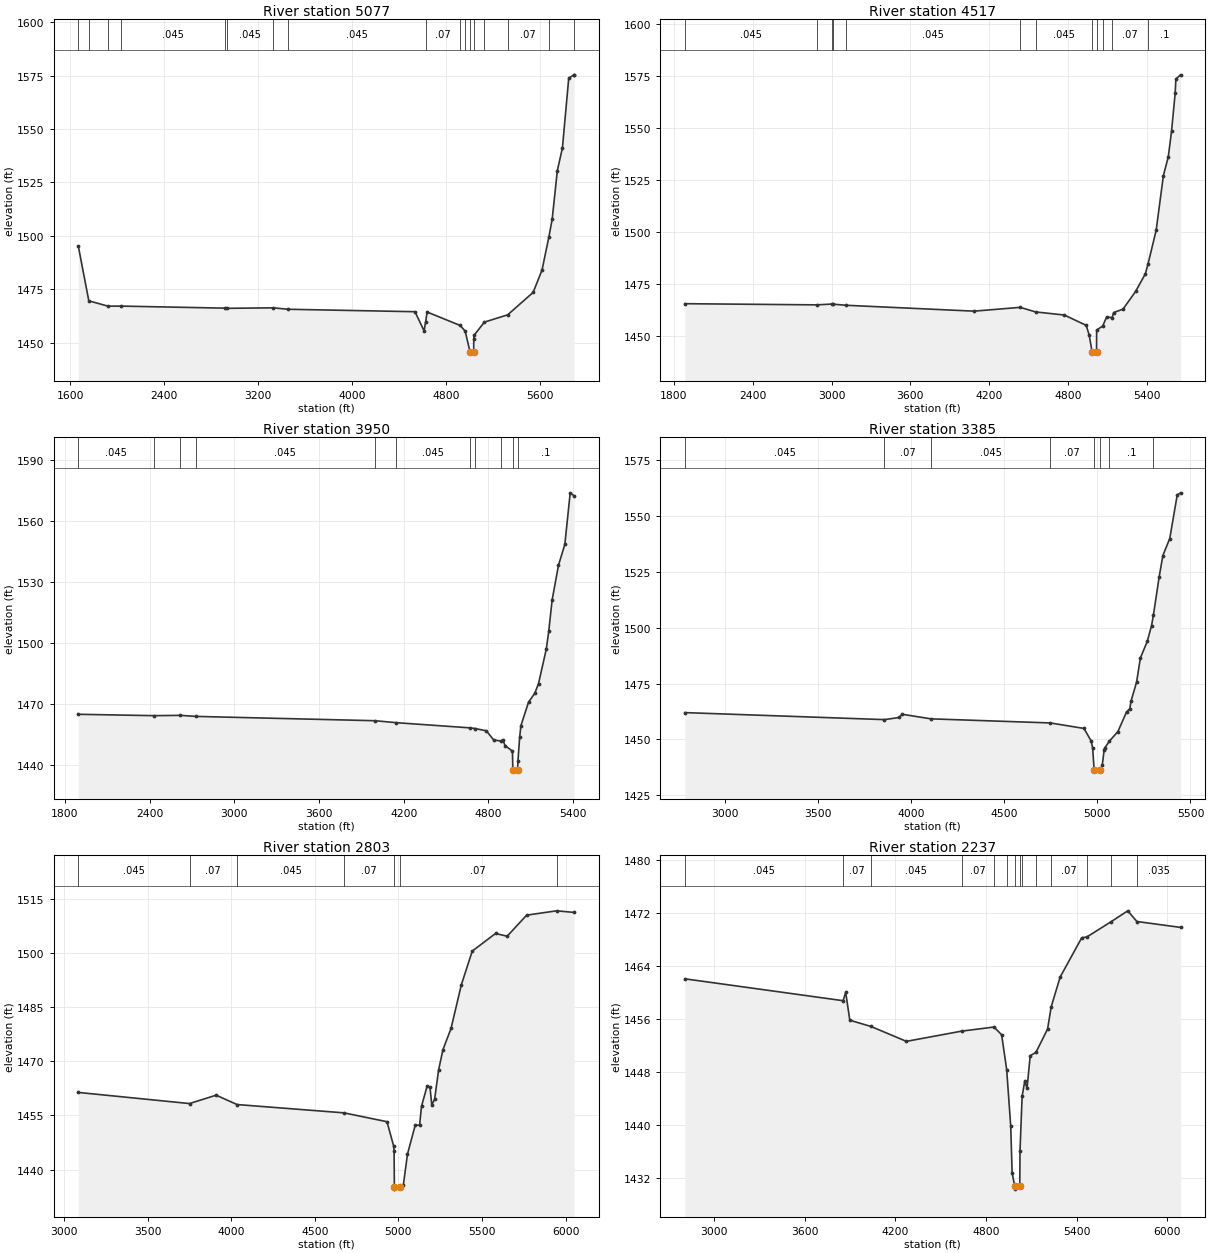
Type RM Length L Ch R = 1,5077,560,560,560
BEGIN DESCRIPTION:
Cherry Creek 9.0
END DESCRIPTION:
XS GIS Cut Line= 4
      1975410.39     13885225.17      1977813.79     13884369.73
      1978375.00     13883825.00      1979174.97     13883425.02
#Sta/Elev= 30
  1667.0 1495.13  1756.4 1469.56  1919.3 1467.07  2031.8 1467.09  2916.5 1466.13
  2933.8 1466.05  3327.7 1466.28  3454.0 1465.61  4537.4 1464.46  4614.9 1455.50
  4628.6 1459.79  4640.8 1464.32  4922.4 1458.03  4965.1 1455.39  5007.2 1445.56
  5007.7 1445.06  5037.9 1445.56  5038.5 1451.73  5043.5 1453.56  5129.0 1459.59
  5328.1 1463.01  5545.0 1473.53  5620.4 1483.94  5678.6 1499.35  5707.1 1507.71
  5751.2 1530.60  5794.3 1541.09  5848.5 1573.93  5893.6 1575.42  5894.6 1575.43
#Mann=17,-1,0
  1667.0    0.07       0  1756.4   0.035       0  1919.3    0.07       0
  2031.8   0.045       0  2916.5    0.07       0  2933.8   0.045       0
  3327.7    0.07       0  3454.0   0.045       0  4628.6    0.07       0
  4922.4   0.035       0  4965.1     0.1       0  5007.2    0.05       0
  5037.9     0.1       0  5129.0   0.035       0  5328.1    0.07       0
  5678.6     0.1       0  5893.6    0.07       0
Bank Sta=5007.2,5037.9
Exp/Cntr=0.3,0.1

Type RM Length L Ch R = 1,4517,567,567,567
BEGIN DESCRIPTION:
Cherry Creek 8.0
END DESCRIPTION:
XS GIS Cut Line= 3
      1976033.08     13885526.30      1978825.00     13884125.00
      1979375.02     13883774.99
#Sta/Elev= 30
  1882.2 1465.34  2887.2 1464.78  3002.0 1465.17  3012.0 1465.11  3111.3 1464.58
  4085.2 1461.75  4436.2 1463.58  4554.1 1461.37  4771.7 1459.89  4939.3 1454.91
  4962.1 1450.12  4984.1 1442.02  4984.7 1441.52  5017.5 1442.02  5018.4 1452.61
  5064.9 1454.63  5094.6 1458.95  5136.1 1458.62  5148.0 1461.07  5219.1 1462.71
  5315.1 1471.24  5389.8 1479.77  5410.2 1484.60  5471.5 1500.63  5526.9 1527.11
  5564.0 1536.11  5588.9 1548.49  5616.3 1566.69  5621.9 1573.64  5658.0 1575.64
#Mann=12,-1,0
  1882.2   0.045       0  2887.2   0.035       0  3002.0   0.045       0
  3012.0    0.07       0  3111.3   0.045       0  4436.2    0.07       0
  4554.1   0.045       0  4984.1   0.045       0  5017.5   0.045       0
  5064.9     0.1       0  5136.1    0.07       0  5410.2     0.1       0
Bank Sta=4984.1,5017.5
Exp/Cntr=0.3,0.1

Type RM Length L Ch R = 1,3950,565,565,565
BEGIN DESCRIPTION:
Cherry Creek 7.0
END DESCRIPTION:
XS GIS Cut Line= 3
      1976351.39     13885659.60      1979225.00     13884475.00
      1979574.99     13884275.01
#Sta/Elev= 30
  1895.7 1464.83  2430.7 1464.15  2619.1 1464.30  2727.1 1463.79  3996.5 1461.66
  4148.7 1460.69  4671.2 1458.13  4708.2 1457.78  4785.1 1456.69  4837.0 1452.19
  4887.2 1451.68  4901.5 1452.15  4918.1 1449.40  4970.1 1446.65  4972.8 1437.31
  4973.4 1436.81  5006.3 1437.31  5009.2 1441.96  5021.3 1453.76  5030.1 1459.27
  5084.1 1470.82  5128.0 1475.16  5154.5 1479.92  5209.7 1496.97  5226.9 1505.66
  5251.2 1521.27  5296.1 1538.31  5341.0 1548.59  5379.0 1574.00  5407.0 1572.48
#Mann=11,-1,0
  1895.7   0.045       0  2430.7    0.07       0  2619.1   0.035       0
  2727.1   0.045       0  3996.5    0.07       0  4148.7   0.045       0
  4671.2    0.07       0  4708.2   0.045       0  4887.2    0.07       0
  4972.8    0.05       0  5006.3     0.1       0
Bank Sta=4972.8,5006.3
Exp/Cntr=0.3,0.1

Type RM Length L Ch R = 1,3385,582,582,582
BEGIN DESCRIPTION:
Cherry Creek 6.0
END DESCRIPTION:
XS GIS Cut Line= 3
      1977231.04     13885878.75      1979275.00     13885025.00
      1979674.99     13884825.01
#Sta/Elev= 30
  2785.0 1462.00  3856.6 1458.86  3935.9 1459.81  3952.1 1461.26  4106.4 1459.21
  4747.8 1457.37  4928.3 1454.91  4967.3 1449.24  4975.1 1446.07  4983.0 1436.29
  4983.7 1435.79  5016.5 1436.29  5026.6 1438.52  5036.7 1445.26  5040.0 1446.18
  5064.0 1449.12  5110.5 1453.51  5157.4 1462.37  5174.2 1463.71  5180.9 1467.09
  5211.1 1475.76  5231.2 1486.44  5268.1 1493.89  5291.1 1500.90  5300.9 1505.52
  5331.8 1522.65  5352.0 1532.35  5388.9 1539.95  5429.1 1559.50  5447.3 1560.43
#Mann=8,-1,0
  2785.0   0.045       0  3856.6    0.07       0  4106.4   0.045       0
  4747.8    0.07       0  4983.0    0.05       0  5016.5    0.07       0
  5064.0     0.1       0  5300.9    0.07       0
Bank Sta=4983,5016.5
Exp/Cntr=0.3,0.1

Type RM Length L Ch R = 1,2803,566,566,566
BEGIN DESCRIPTION:
Cherry Creek 5.0
END DESCRIPTION:
XS GIS Cut Line= 4
      1977501.11     13885963.23      1979375.00     13885575.00
      1979944.81     13885269.48      1980162.02     13884928.64
#Sta/Elev= 30
  3086.3 1461.40  3751.1 1458.31  3910.3 1460.64  4034.9 1458.04  4674.5 1455.73
  4931.8 1453.27  4971.1 1446.58  4974.2 1445.26  4975.8 1435.05  4976.4 1434.55
  5009.3 1435.05  5029.2 1435.58  5054.2 1444.28  5100.6 1452.32  5126.6 1452.29
  5138.1 1457.55  5170.9 1463.06  5188.6 1462.94  5199.4 1457.94  5216.4 1459.48
  5240.2 1467.65  5266.2 1473.25  5314.5 1479.16  5376.4 1491.32  5441.5 1500.65
  5580.6 1505.54  5650.1 1504.78  5766.8 1510.63  5945.3 1511.83  6050.7 1511.39
#Mann=7,-1,0
  3086.3   0.045       0  3751.1    0.07       0  4034.9   0.045       0
  4674.5    0.07       0  4975.8    0.05       0  5009.3    0.07       0
  5945.3   0.035       0
Bank Sta=4975.8,5009.3
Exp/Cntr=0.3,0.1

Type RM Length L Ch R = 1,2237,563,563,563
BEGIN DESCRIPTION:
Cherry Creek 4.0
END DESCRIPTION:
XS GIS Cut Line= 3
      1977242.64     13886364.22      1979425.00     13886125.00
      1980410.77     13886587.24
#Sta/Elev= 30
  2804.4 1462.07  3852.9 1458.77  3870.1 1460.03  3897.3 1455.83  4038.1 1454.88
  4272.2 1452.64  4637.8 1454.18  4852.7 1454.80  4903.0 1453.63  4936.4 1448.39
  4963.3 1439.84  4972.4 1432.84  4989.2 1430.86  4989.9 1430.36  5023.1 1430.86
  5024.7 1436.09  5038.7 1444.35  5055.9 1446.63  5071.3 1445.57  5092.3 1450.48
  5130.1 1450.97  5207.4 1454.50  5231.3 1457.85  5291.1 1462.36  5433.6 1468.26
  5467.7 1468.38  5626.8 1470.66  5738.4 1472.32  5798.8 1470.71  6088.6 1469.82
#Mann=14,-1,0
  2804.4   0.045       0  3852.9    0.07       0  4038.1   0.045       0
  4637.8    0.07       0  4852.7   0.035       0  4936.4    0.07       0
  4989.2    0.05       0  5023.1    0.07       0  5038.7     0.1       0
  5130.1   0.035       0  5231.3    0.07       0  5467.7   0.035       0
  5626.8    0.07       0  5798.8   0.035       0
Bank Sta=4989.2,5023.1
Exp/Cntr=0.3,0.1

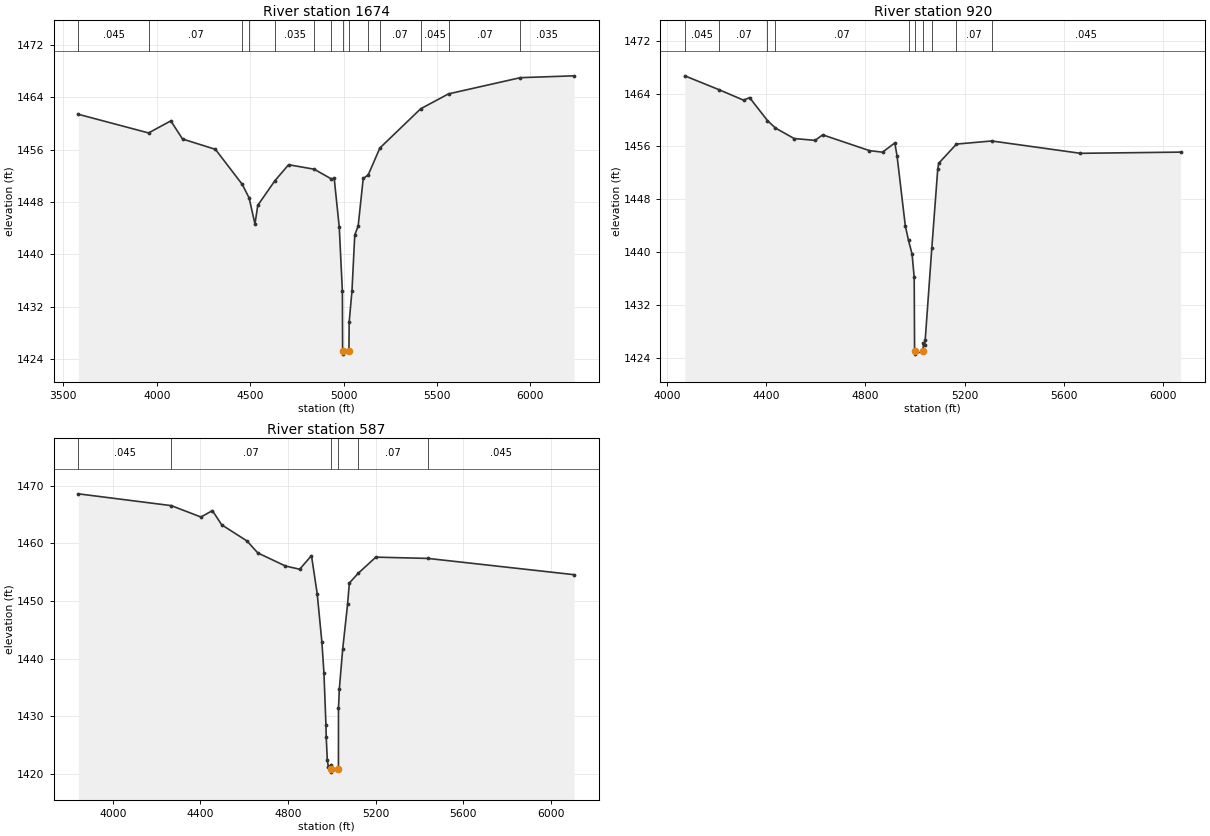
Type RM Length L Ch R = 1,1674,754,754,754
BEGIN DESCRIPTION:
Cherry Creek 3.0
END DESCRIPTION:
XS GIS Cut Line= 3
      1977810.01     13886630.42      1979225.00     13886625.00
      1980458.58     13886746.96
#Sta/Elev= 30
  3580.2 1461.41  3956.2 1458.56  4075.2 1460.40  4138.2 1457.63  4314.2 1456.05
  4457.9 1450.69  4494.3 1448.64  4525.9 1444.64  4540.9 1447.49  4632.5 1451.25
  4705.9 1453.70  4843.1 1453.01  4934.1 1451.54  4950.1 1451.62  4977.2 1444.14
  4993.9 1434.35  4995.1 1425.24  4995.7 1424.74  5029.0 1425.24  5030.1 1429.58
  5045.2 1434.39  5060.2 1442.97  5078.3 1444.31  5105.5 1451.60  5132.0 1452.13
  5194.5 1456.25  5412.9 1462.25  5562.1 1464.53  5946.9 1467.01  6234.8 1467.29
#Mann=14,-1,0
  3580.2   0.045       0  3956.2    0.07       0  4457.9   0.035       0
  4494.3    0.07       0  4632.5   0.035       0  4843.1    0.07       0
  4934.1   0.035       0  4995.1    0.05       0  5029.0   0.035       0
  5132.0   0.045       0  5194.5    0.07       0  5412.9   0.045       0
  5562.1    0.07       0  5946.9   0.035       0
Bank Sta=4995.1,5029
Exp/Cntr=0.3,0.1

Type RM Length L Ch R = 1,920,333,333,333
BEGIN DESCRIPTION:
Cherry Creek 2.0
END DESCRIPTION:
XS GIS Cut Line= 3
      1978043.30     13887158.56      1978967.88     13887288.06
      1980018.29     13887466.10
#Sta/Elev= 30
  4072.2 1466.69  4211.4 1464.57  4309.2 1463.00  4333.4 1463.39  4405.6 1459.90
  4437.8 1458.78  4512.9 1457.19  4597.7 1456.91  4628.0 1457.75  4816.4 1455.36
  4869.5 1455.12  4918.8 1456.52  4927.9 1454.57  4961.2 1443.97  4974.1 1441.76
  4988.5 1439.67  4997.1 1436.14  4998.6 1425.02  4999.3 1424.52  5033.0 1425.02
  5034.0 1426.26  5038.9 1425.96  5041.5 1426.71  5068.2 1440.65  5091.9 1452.50
  5096.1 1453.45  5167.6 1456.35  5309.8 1456.82  5666.9 1454.95  6071.2 1455.13
#Mann=10,-1,0
  4072.2   0.045       0  4211.4    0.07       0  4405.6   0.045       0
  4437.8    0.07       0  4974.1     0.1       0  4998.6    0.05       0
  5033.0     0.1       0  5068.2   0.035       0  5167.6    0.07       0
  5309.8   0.045       0
Bank Sta=4998.6,5033
Exp/Cntr=0.3,0.1

Type RM Length L Ch R = 1,587,0,0,0
BEGIN DESCRIPTION:
Cherry Creek 1.0
END DESCRIPTION:
XS GIS Cut Line= 3
      1977702.78     13887309.51      1978825.00     13887575.00
      1979919.74     13887770.75
#Sta/Elev= 30
  3842.1 1468.61  4266.8 1466.56  4402.4 1464.58  4454.6 1465.70  4497.0 1463.23
  4613.1 1460.41  4662.1 1458.34  4788.5 1456.07  4853.2 1455.51  4907.3 1457.87
  4933.4 1451.26  4954.9 1442.83  4964.2 1437.50  4973.4 1428.44  4974.6 1426.37
  4979.6 1422.38  4984.6 1421.11  4995.3 1421.52  4996.1 1420.76  4996.8 1420.26
  5030.5 1420.76  5030.7 1431.33  5034.6 1434.73  5049.9 1441.62  5072.1 1449.40
  5080.3 1453.12  5121.7 1454.84  5201.3 1457.61  5438.9 1457.39  6107.4 1454.56
#Mann=6,-1,0
  3842.1   0.045       0  4266.8    0.07       0  4996.1    0.05       0
  5030.5    0.07       0  5121.7    0.07       0  5438.9   0.045       0
Bank Sta=4996.1,5030.5
Exp/Cntr=0.3,0.1

Chan Stop Cuts=-1