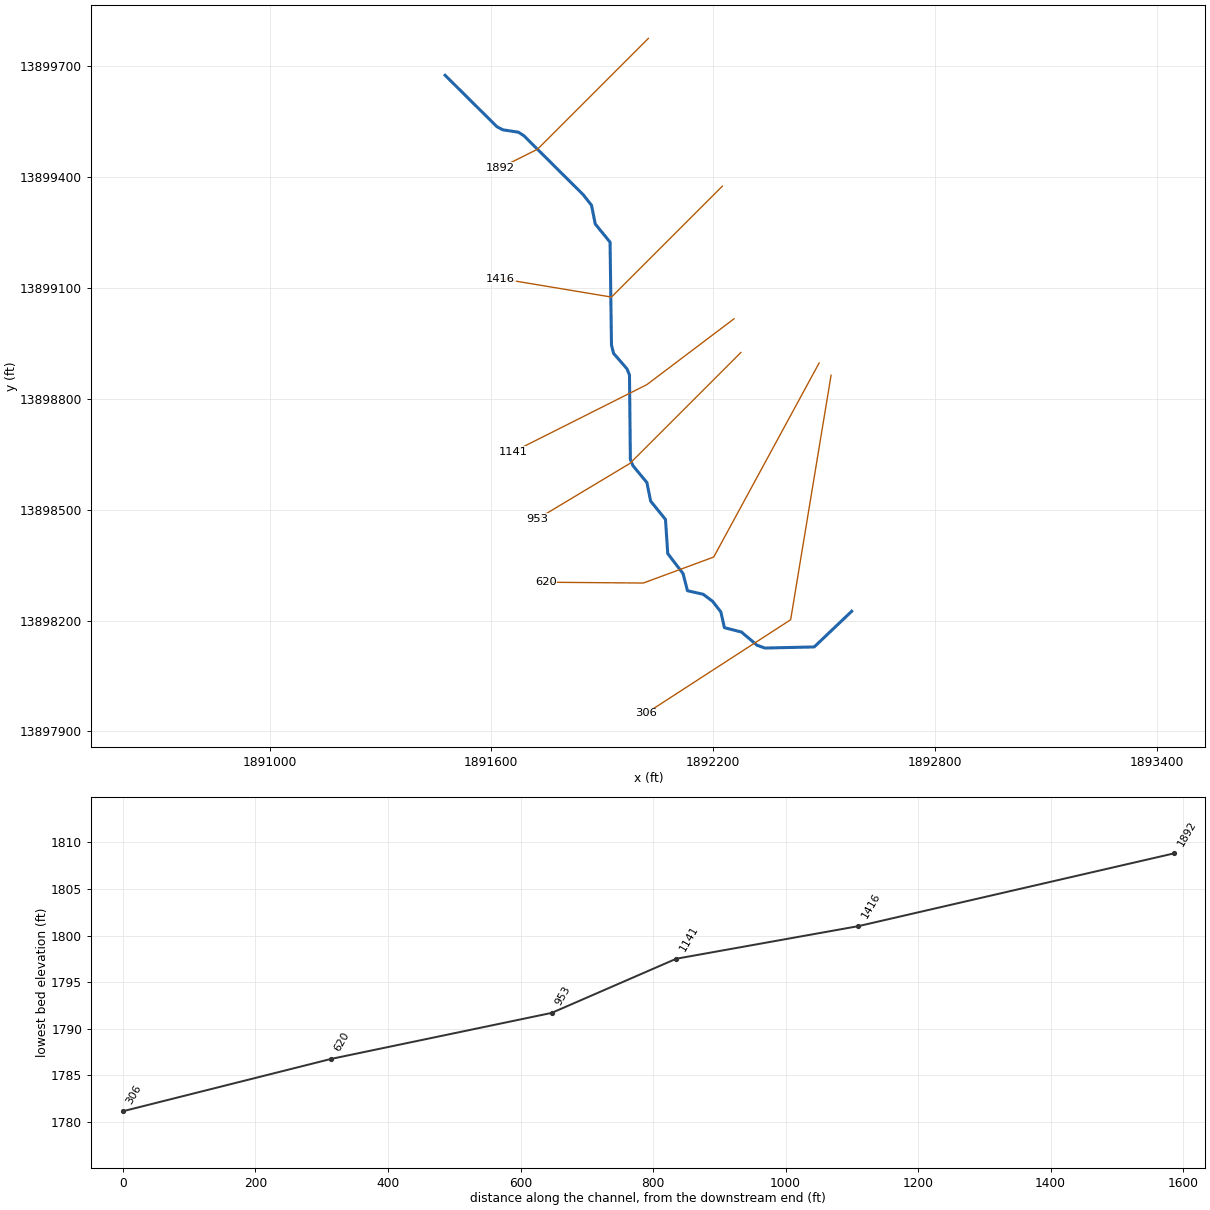
--- Coker Hollow.prj (project) ---

Proj Title=Coker Hollow Base Level Engineering
Current Plan=p01
Default Exp/Contr=0.3,0.1
English Units
Geom File=g01
Flow File=f01
Plan File=p01
BEGIN DESCRIPTION:
Coker Hollow
END DESCRIPTION:

--- Coker Hollow.p01 (plan) ---

Plan Title=Multiple Run
Short Identifier=Multiple
Geom File=g01
Flow File=f01
Subcritical Flow
K Sum by GR= 0
Std Step Tol= 0.01
Critical Tol= 0.01
Num of Std Step Trials= 20
Max Error Tol= 0.3
Flow Tol Ratio= 0.001
Split Flow NTrial= 30
Split Flow Tol= 0.02
Split Flow Ratio= 0.02
Log Output Level= 0
Friction Slope Method= 1
Unsteady Friction Slope Method= 2
Unsteady Bridges Friction Slope Method= 1
Parabolic Critical Depth
Global Vel Dist=  1 , 1 , 1
Global Log Level= 0
CheckData=True
Encroach Param= -1, 0, 0, 0
BEGIN DESCRIPTION:
Multiple Run
END DESCRIPTION:

--- Coker Hollow.f01 (steady flow) ---

Flow Title=Multiple
Number of Profiles=7
Profile Names=10-year,25-year,50-year,1pct_min,100-year,1pct_plu,500-year
River Rch & RM= Coker Hollow,Reach-1,1892
    1233    2134    3006    2050    4089    8159    7472
Boundary for River Rch & Prof#=Coker Hollow,Reach-1,1
Up Type=0
Dn Type=3
Dn Slope=0.005
Boundary for River Rch & Prof#=Coker Hollow,Reach-1,2
Up Type=0
Dn Type=3
Dn Slope=0.005
Boundary for River Rch & Prof#=Coker Hollow,Reach-1,3
Up Type=0
Dn Type=3
Dn Slope=0.005
Boundary for River Rch & Prof#=Coker Hollow,Reach-1,4
Up Type=0
Dn Type=3
Dn Slope=0.005
Boundary for River Rch & Prof#=Coker Hollow,Reach-1,5
Up Type=0
Dn Type=3
Dn Slope=0.005
Boundary for River Rch & Prof#=Coker Hollow,Reach-1,6
Up Type=0
Dn Type=3
Dn Slope=0.005
Boundary for River Rch & Prof#=Coker Hollow,Reach-1,7
Up Type=0
Dn Type=3
Dn Slope=0.005

--- Coker Hollow.g01 (geometry) ---

Geom Title=Existing Conditions

River Reach=Coker Hollow,Reach-1
Reach XY= 30
      1891475.00     13899675.00      1891615.32     13899535.77
      1891631.05     13899527.53      1891673.35     13899521.02
      1891688.21     13899511.37      1891848.71     13899351.82
      1891871.06     13899323.37      1891881.14     13899272.83
      1891921.25     13899223.45      1891925.07     13898945.03
      1891930.75     13898922.67      1891966.86     13898881.06
      1891973.78     13898864.50      1891976.20     13898635.50
      1891983.09     13898618.92      1892020.81     13898573.26
      1892031.11     13898522.82      1892071.17     13898473.41
      1892077.32     13898380.94      1892118.73     13898326.84
      1892130.62     13898280.62      1892173.19     13898270.93
      1892198.65     13898251.96      1892220.93     13898223.19
      1892230.62     13898180.62      1892276.84     13898168.72
      1892318.88     13898133.07      1892340.20     13898125.48
      1892473.55     13898128.48      1892575.00     13898225.00

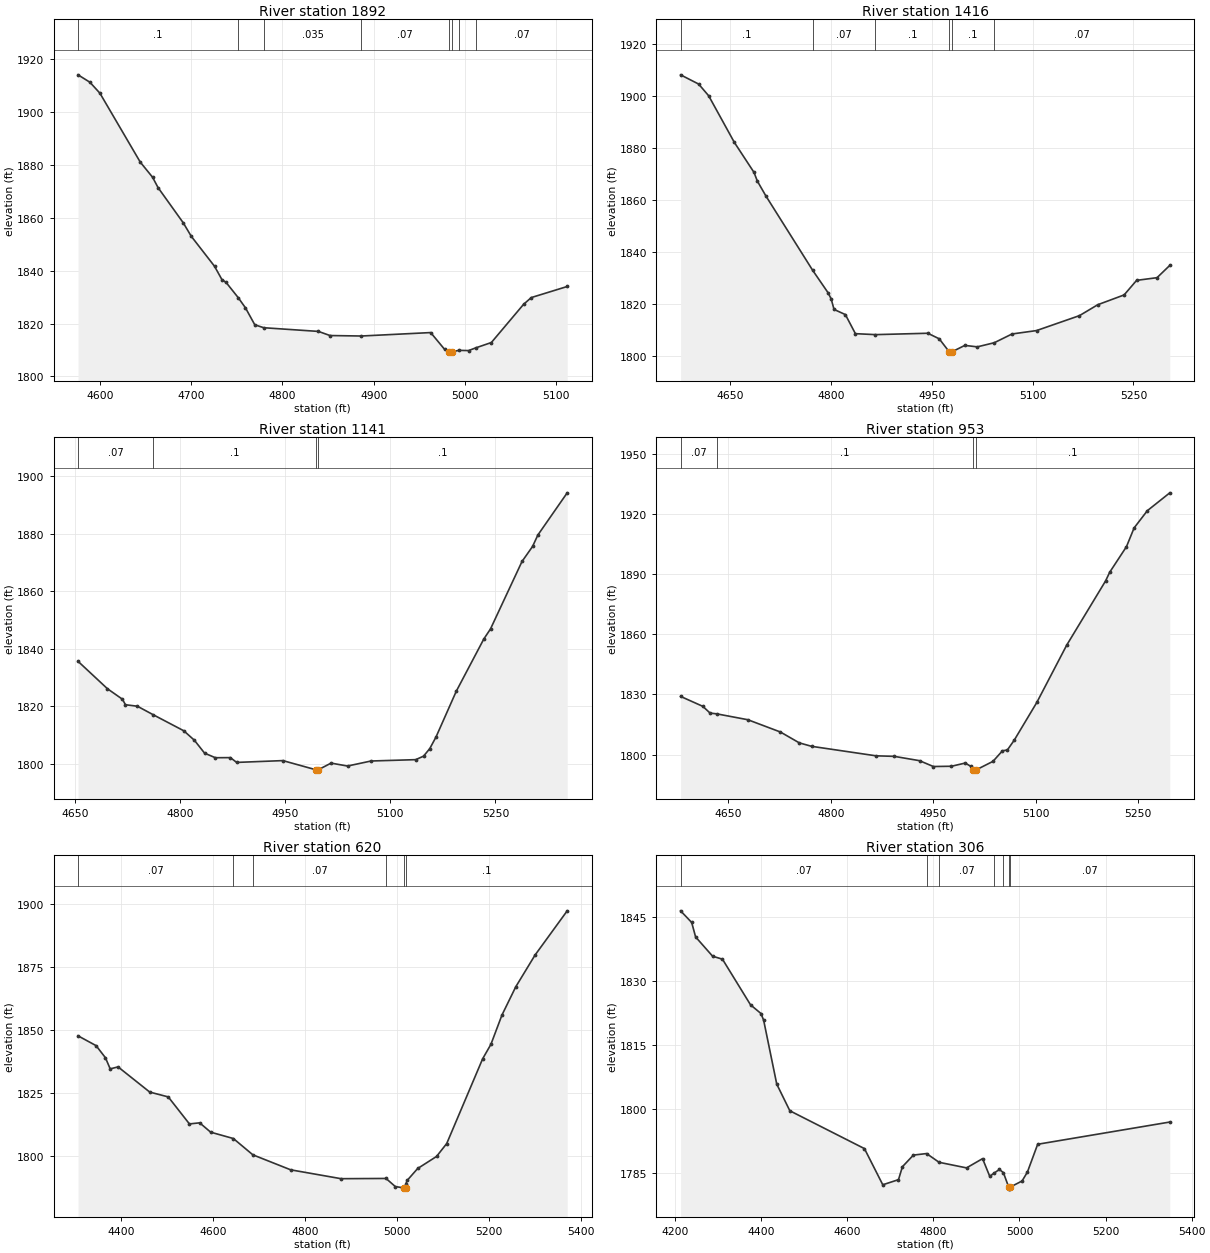
Type RM Length L Ch R = 1,1892,476,476,476
BEGIN DESCRIPTION:
Stream0593 3.0
END DESCRIPTION:
XS GIS Cut Line= 3
      1892024.97     13899774.97      1891725.00     13899475.00
      1891625.02     13899425.01
#Sta/Elev= 30
  4576.0 1914.03  4589.0 1911.24  4600.0 1907.09  4644.2 1881.04  4657.7 1875.31
  4663.7 1871.40  4691.3 1858.09  4700.1 1852.99  4725.6 1841.65  4733.7 1836.61
  4738.3 1835.53  4751.5 1829.81  4759.5 1825.93  4769.7 1819.53  4779.6 1818.42
  4839.4 1817.03  4852.1 1815.47  4886.5 1815.29  4962.4 1816.59  4977.6 1810.27
  4982.0 1809.32  4982.3 1808.82  4986.0 1809.32  4993.3 1809.87  5003.9 1809.78
  5011.8 1810.81  5028.9 1812.83  5064.2 1827.27  5072.6 1829.82  5112.0 1834.01
#Mann=8,-1,0
  4576.0     0.1       0  4751.5    0.07       0  4779.6   0.035       0
  4886.5    0.07       0  4982.0    0.05       0  4986.0    0.07       0
  4993.3     0.1       0  5011.8    0.07       0
Bank Sta=4982,4986
Exp/Cntr=0.3,0.1

Type RM Length L Ch R = 1,1416,275,275,275
BEGIN DESCRIPTION:
Stream0593 2.0
END DESCRIPTION:
XS GIS Cut Line= 3
      1892225.02     13899375.02      1891925.00     13899075.00
      1891625.03     13899124.99
#Sta/Elev= 30
  4575.7 1907.99  4602.6 1904.44  4617.5 1899.95  4655.7 1882.04  4685.0 1870.50
  4690.0 1867.15  4702.7 1861.44  4772.3 1832.88  4795.3 1824.23  4799.9 1821.86
  4804.2 1817.82  4821.1 1815.83  4836.0 1808.50  4865.9 1808.13  4943.8 1808.66
  4960.8 1806.53  4975.7 1801.52  4976.0 1801.02  4979.7 1801.52  4998.9 1803.99
  5017.5 1803.43  5042.8 1805.02  5069.2 1808.38  5105.7 1809.69  5169.6 1815.43
  5196.9 1819.63  5236.1 1823.39  5254.7 1828.99  5285.1 1830.02  5304.1 1834.74
#Mann=6,-1,0
  4575.7     0.1       0  4772.3    0.07       0  4865.9     0.1       0
  4975.7    0.05       0  4979.7     0.1       0  5042.8    0.07       0
Bank Sta=4975.7,4979.7
Exp/Cntr=0.3,0.1

Type RM Length L Ch R = 1,1141,188,188,188
BEGIN DESCRIPTION:
Mapping XS 7ccb83a4
END DESCRIPTION:
XS GIS Cut Line= 3
      1892256.64     13899016.22      1892020.85     13898838.18
      1891660.29     13898656.95
#Sta/Elev= 30
  4653.6 1835.72  4695.7 1826.17  4717.1 1822.52  4721.4 1820.61  4738.5 1820.09
  4761.3 1817.10  4804.7 1811.56  4819.9 1808.26  4834.5 1803.76  4849.9 1802.18
  4871.3 1802.22  4880.3 1800.55  4946.3 1801.18  4993.1 1798.02  4993.3 1797.52
  4997.1 1798.02  5015.2 1800.31  5038.7 1799.29  5072.3 1801.04  5136.1 1801.51
  5147.3 1802.72  5156.2 1805.35  5165.1 1809.37  5194.2 1825.36  5233.5 1843.50
  5243.0 1846.98  5288.0 1870.43  5303.1 1875.66  5310.7 1879.65  5352.6 1894.31
#Mann=4,-1,0
  4653.6    0.07       0  4761.3     0.1       0  4993.1    0.05       0
  4997.1     0.1       0
Bank Sta=4993.1,4997.1
Exp/Cntr=0.3,0.1

Type RM Length L Ch R = 1,953,333,333,333
BEGIN DESCRIPTION:
Stream0593 1.0
END DESCRIPTION:
XS GIS Cut Line= 3
      1892275.03     13898925.03      1891975.00     13898625.00
      1891724.96     13898474.98
#Sta/Elev= 30
  4580.2 1828.98  4612.8 1824.01  4623.4 1820.65  4632.9 1820.29  4678.6 1817.35
  4726.3 1811.22  4753.9 1805.81  4771.9 1804.08  4866.3 1799.34  4892.8 1799.08
  4929.9 1796.92  4950.1 1794.01  4976.6 1794.14  4996.8 1795.74  5004.5 1794.17
  5008.0 1792.21  5008.2 1791.71  5012.0 1792.21  5037.4 1796.59  5051.2 1801.84
  5058.4 1802.26  5068.3 1807.06  5101.5 1825.96  5145.2 1854.52  5202.1 1886.55
  5208.2 1890.92  5232.7 1903.66  5243.9 1913.02  5263.3 1921.62  5296.1 1930.51
#Mann=4,-1,0
  4580.2    0.07       0  4632.9     0.1       0  5008.0    0.05       0
  5012.0     0.1       0
Bank Sta=5008,5012
Exp/Cntr=0.3,0.1

Type RM Length L Ch R = 1,620,314,314,314
BEGIN DESCRIPTION:
Stream0593 0.0
END DESCRIPTION:
XS GIS Cut Line= 4
      1892486.84     13898896.69      1892201.66     13898371.68
      1892011.30     13898301.38      1891747.81     13898303.53
#Sta/Elev= 30
  4305.5 1847.71  4344.8 1843.81  4365.2 1838.99  4375.5 1834.57  4392.6 1835.36
  4461.5 1825.35  4501.8 1823.42  4547.8 1812.69  4570.1 1813.12  4594.0 1809.41
  4643.4 1806.88  4685.8 1800.40  4768.1 1794.44  4877.6 1790.92  4975.4 1791.01
  4995.6 1787.78  5014.2 1787.27  5014.4 1786.77  5018.2 1787.27  5018.5 1788.85
  5021.2 1790.20  5044.2 1794.97  5085.2 1799.75  5107.4 1804.90  5185.5 1838.58
  5203.5 1844.33  5227.5 1855.97  5257.5 1867.19  5299.5 1879.82  5369.4 1897.39
#Mann=6,-1,0
  4305.5    0.07       0  4643.4     0.1       0  4685.8    0.07       0
  4975.4     0.1       0  5014.2    0.05       0  5018.2     0.1       0
Bank Sta=5014.2,5018.2
Exp/Cntr=0.3,0.1

Type RM Length L Ch R = 1,306,0,0,0
BEGIN DESCRIPTION:
Stream0593 0.1
END DESCRIPTION:
XS GIS Cut Line= 3
      1892519.17     13898863.60      1892409.79     13898202.11
      1892018.77     13897948.75
#Sta/Elev= 30
  4212.8 1846.41  4238.6 1843.68  4247.7 1840.29  4287.2 1835.77  4310.1 1835.07
  4375.3 1824.37  4399.7 1822.32  4405.8 1820.74  4436.2 1805.78  4466.6 1799.53
  4639.9 1790.66  4682.5 1782.18  4719.0 1783.38  4728.1 1786.41  4753.6 1789.14
  4784.2 1789.50  4813.3 1787.45  4877.1 1786.14  4914.3 1788.31  4931.0 1784.15
  4940.8 1784.90  4953.4 1785.77  4962.7 1785.02  4974.9 1781.66  4975.2 1781.16
  4978.9 1781.66  5006.1 1783.07  5018.5 1785.17  5042.3 1791.68  5349.2 1796.89
#Mann=7,-1,0
  4212.8    0.07       0  4784.2     0.1       0  4813.3    0.07       0
  4940.8     0.1       0  4962.7    0.07       0  4974.9    0.05       0
  4978.9    0.07       0
Bank Sta=4974.9,4978.9
Exp/Cntr=0.3,0.1

Chan Stop Cuts=-1