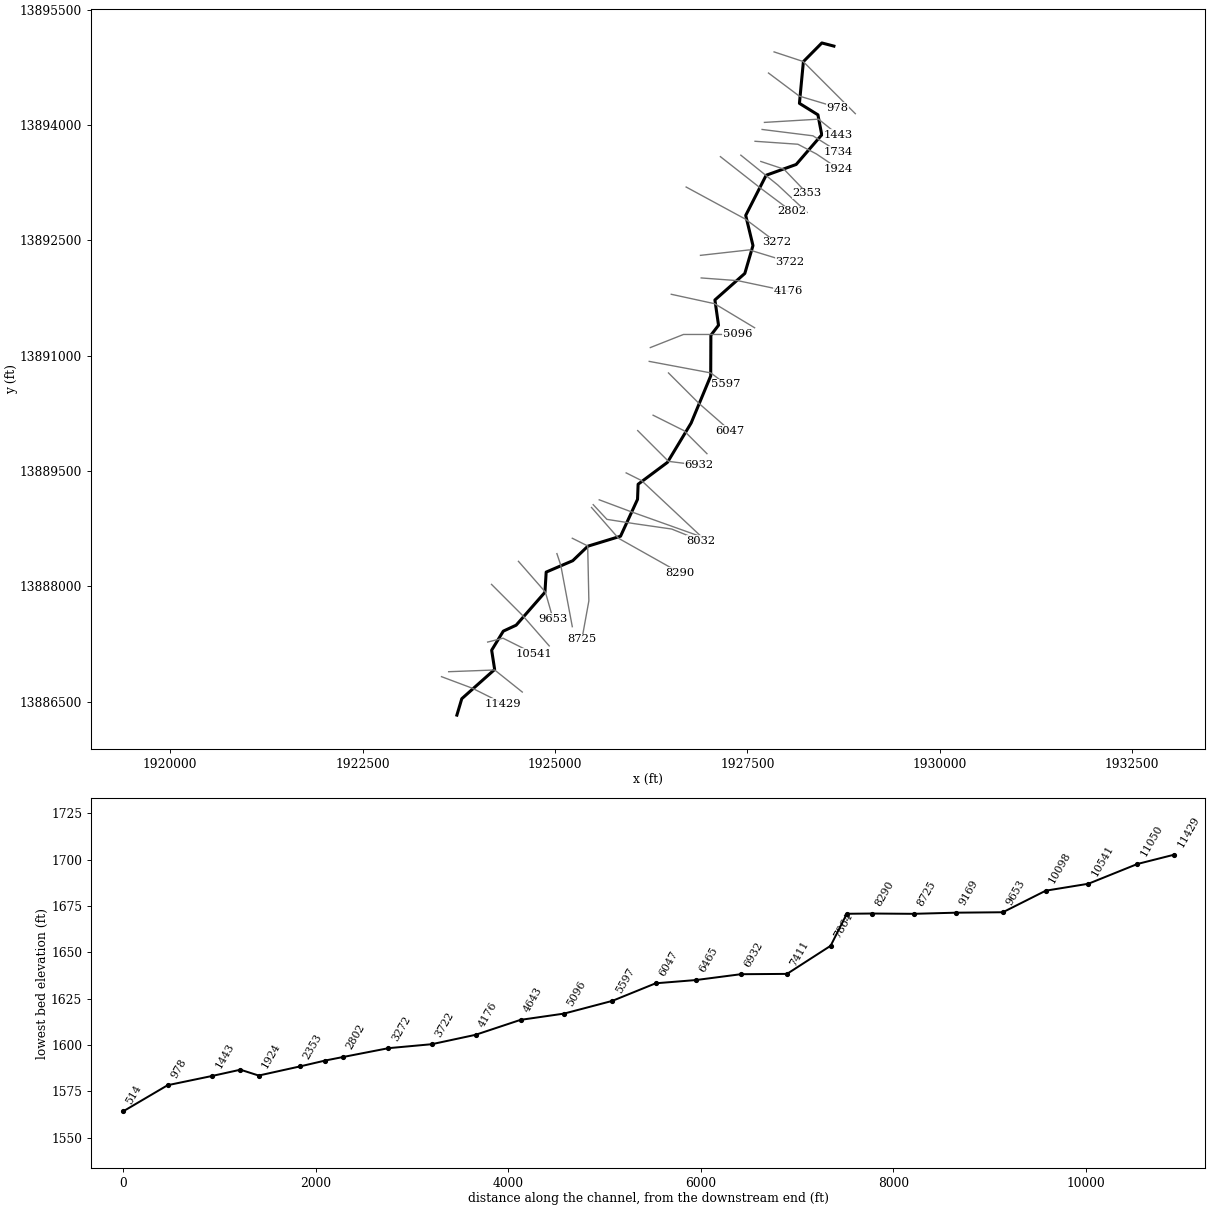
--- Cow Creek.prj (project) ---

Proj Title=Cow Creek Base Level Engineering
Current Plan=p01
Default Exp/Contr=0.3,0.1
English Units
Geom File=g01
Flow File=f01
Plan File=p01
Y Axis Title=Elevation
X Axis Title(PF)=Main Channel Distance
X Axis Title(XS)=Station
BEGIN DESCRIPTION:
Cow Creek
END DESCRIPTION:
DSS Export Rating Curves= 0
DSS Export Rating Curve Sorted= 0
DSS Export Volume Flow Curves= 0
DXF OffsetX= 0
DXF OffsetY= 0
DXF ScaleX= 1
DXF ScaleY= 10

--- Cow Creek.p01 (plan) ---

Plan Title=Multiple Run
Short Identifier=Multiple
Geom File=g01
Flow File=f01
Subcritical Flow
K Sum by GR= 0
Std Step Tol= 0.01
Critical Tol= 0.01
Num of Std Step Trials= 20
Max Error Tol= 0.3
Flow Tol Ratio= 0.001
Split Flow NTrial= 30
Split Flow Tol= 0.02
Split Flow Ratio= 0.02
Log Output Level= 0
Friction Slope Method= 1
Unsteady Friction Slope Method= 2
Unsteady Bridges Friction Slope Method= 1
Parabolic Critical Depth
Global Vel Dist=  1 , 1 , 1
Global Log Level= 0
CheckData=True
Encroach Param= -1, 0, 0, 0
BEGIN DESCRIPTION:
Multiple Run
END DESCRIPTION:

--- Cow Creek.f01 (steady flow) ---

Flow Title=Multiple
Program Version=4.10
Number of Profiles= 7
Profile Names=10-year,25-year,50-year,1pct_min,100-year,1pct_plu,500-year
River Rch & RM=Cow Creek,Reach-1         ,11429
    2017    3545    5045    3465    6915   13796   12834
River Rch & RM=Cow Creek,Reach-1         ,6932
    2895    5186    7474    5194   10363   20676   19690
River Rch & RM=Cow Creek,Reach-1         ,5096
    3486    6287    9099    6345   12659   25258   24223
Boundary for River Rch & Prof#=Cow Creek,Reach-1         , 1
Up Type= 0
Dn Type= 3
Dn Slope=0.01
Boundary for River Rch & Prof#=Cow Creek,Reach-1         , 2
Up Type= 0
Dn Type= 3
Dn Slope=0.01
Boundary for River Rch & Prof#=Cow Creek,Reach-1         , 3
Up Type= 0
Dn Type= 3
Dn Slope=0.01
Boundary for River Rch & Prof#=Cow Creek,Reach-1         , 4
Up Type= 0
Dn Type= 3
Dn Slope=0.01
Boundary for River Rch & Prof#=Cow Creek,Reach-1         , 5
Up Type= 0
Dn Type= 3
Dn Slope=0.01
Boundary for River Rch & Prof#=Cow Creek,Reach-1         , 6
Up Type= 0
Dn Type= 3
Dn Slope=0.01
Boundary for River Rch & Prof#=Cow Creek,Reach-1         , 7
Up Type= 0
Dn Type= 3
Dn Slope=0.01
DSS Import GetInterval= 0
DSS Import GetPeak= 0
DSS Import FillOption= 0

--- Cow Creek.g01 (geometry) ---

Geom Title=Existing Conditions
Program Version=4.10

River Reach=Cow Creek       ,Reach-1
Reach XY= 30
        1923725.       13886325.      1923788.62     13886538.22
      1924215.72     13886918.32      1924176.97     13887169.11
      1924328.32     13887416.97      1924495.47     13887494.62
      1924869.53     13887922.55      1924885.47     13888184.83
      1925231.06     13888333.14       1925426.5     13888521.39
      1925852.02     13888651.48      1926072.76     13889130.93
      1926080.46     13889327.45      1926461.37     13889611.73
      1926769.17      13890122.7       1927023.8      13890735.5
      1927026.06     13891264.56      1927125.39     13891395.13
      1927078.45     13891723.75      1927467.19     13892068.81
       1927573.2     13892431.11      1927478.74     13892823.44
      1927744.58     13893345.58      1928134.68     13893485.76
      1928467.21     13893871.58      1928417.26     13894131.46
      1928176.97     13894280.65      1928228.54     13894823.53
      1928468.26      13895065.9        1928625.       13895025.

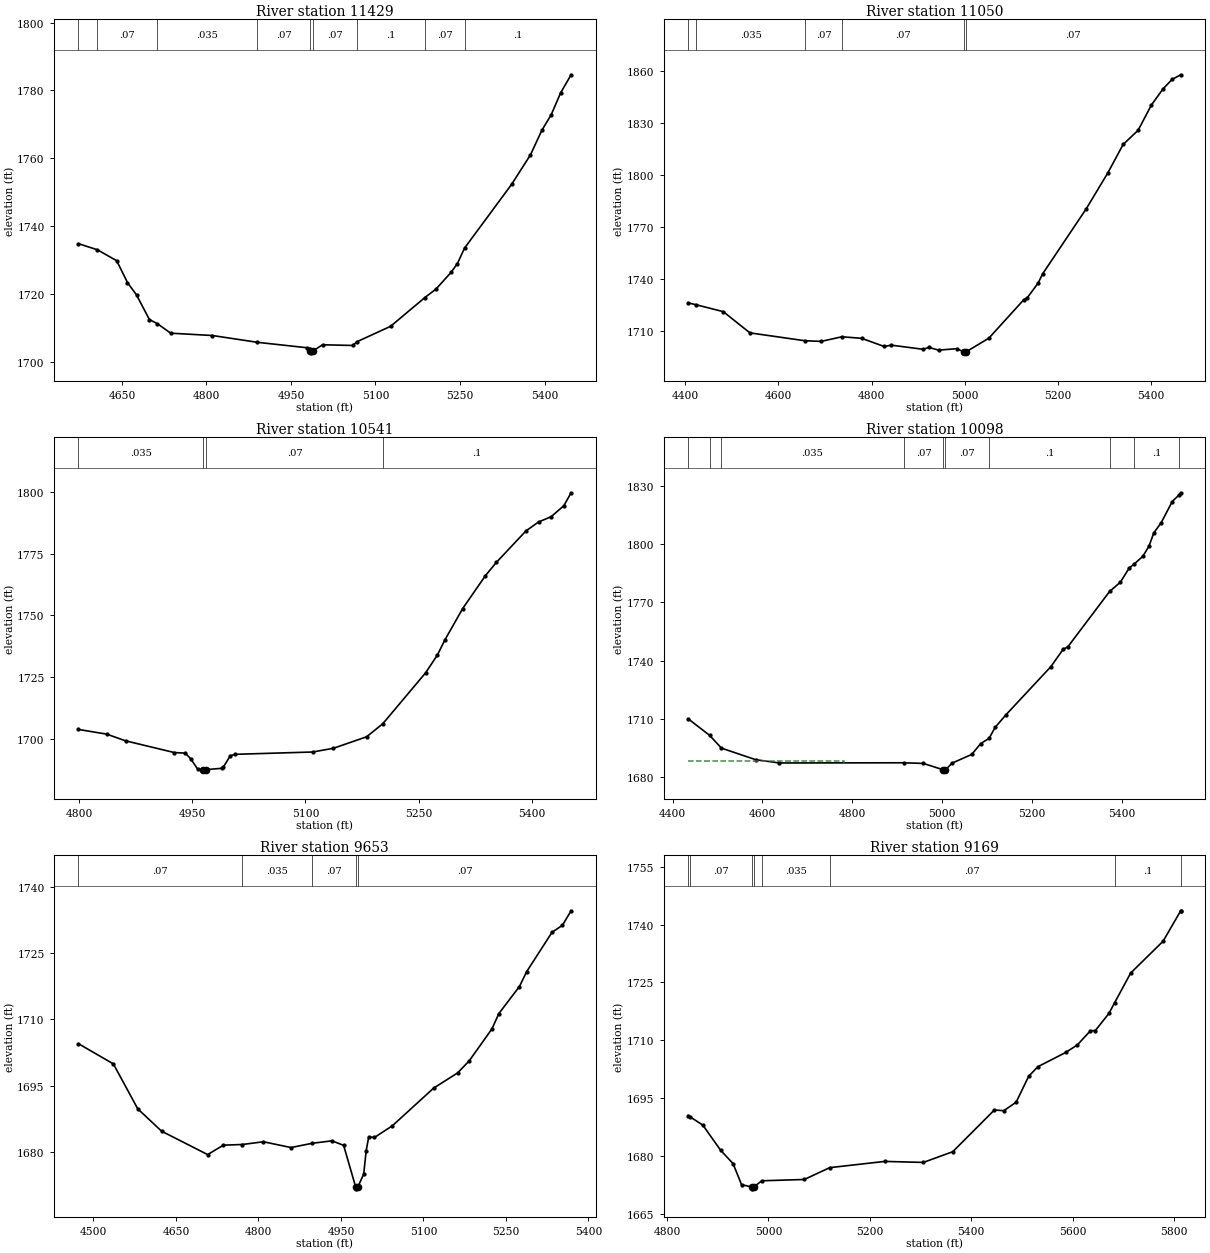
Type RM Length L Ch R = 1 ,11429   ,379,379,379
BEGIN DESCRIPTION:
Cow Creek 24.0
END DESCRIPTION:
XS GIS Cut Line= 3
        1923525.       13886825.        1923925.       13886675.
      1924324.98     13886475.01
#Sta/Elev= 30
  4572.8 1734.82  4606.4 1733.02  4640.6  1729.8  4659.8 1723.35  4675.8 1719.72
  4698.7 1712.45  4712.6 1711.27  4736.6 1708.44  4810.3 1707.76  4890.1 1705.76
    4979 1704.14  4984.1 1703.86  4984.5 1703.15  4984.8 1702.65  4988.6 1703.15
    5006 1705.03  5059.7 1704.82  5066.8  1705.9  5126.8 1710.47  5187.7 1718.95
  5207.3 1721.43  5234.1 1726.35  5245.3 1728.94  5258.2 1733.55  5341.5 1752.28
    5375 1760.97  5395.1 1768.18  5411.9 1772.82  5428.7  1779.3  5447.2  1784.6
#Mann= 9 ,-1 , 0
  4572.8    .035       0  4606.4     .07       0  4712.6    .035       0
  4890.1     .07       0  4984.5     .05       0  4988.6     .07       0
  5066.8      .1       0  5187.7     .07       0  5258.2      .1       0
Bank Sta=4984.5,4988.6
XS Rating Curve= 0 ,0
Exp/Cntr=0.3,0.1

Type RM Length L Ch R = 1 ,11050   ,509,509,509
BEGIN DESCRIPTION:
Cow Creek 23.0
END DESCRIPTION:
XS GIS Cut Line= 3
      1923617.92     13886889.43      1924215.98     13886911.86
      1924574.98     13886625.02
#Sta/Elev= 30
  4406.1 1726.44  4422.3 1725.42  4481.6 1721.37  4538.7 1709.16  4657.7  1704.6
  4691.9 1704.27  4736.3 1706.92  4778.7 1706.03  4826.9 1701.34  4842.4 1702.09
  4910.9  1699.7  4922.9 1700.81    4944 1699.23    4983 1700.07  4998.4 1698.17
  4998.6 1697.67  5002.5 1698.17  5051.9 1706.11  5126.7  1728.2  5134.4 1729.38
  5157.7 1737.81  5167.3 1743.11  5261.1 1780.63  5307.2 1801.17  5340.3 1817.64
  5372.5 1825.82  5400.9 1840.31  5426.2  1849.7  5445.4 1855.09  5464.1 1857.76
#Mann= 6 ,-1 , 0
  4406.1     .07       0  4422.3    .035       0  4657.7     .07       0
  4736.3     .07       0  4998.4     .05       0  5002.5     .07       0
Bank Sta=4998.4,5002.5
XS Rating Curve= 0 ,0
Exp/Cntr=0.3,0.1

Type RM Length L Ch R = 1 ,10541   ,443,443,443
BEGIN DESCRIPTION:
Cow Creek 22.0
END DESCRIPTION:
XS GIS Cut Line= 3
      1924124.99       13887275.        1924325.       13887325.
      1924725.02     13887124.99
#Sta/Elev= 30
    4799 1703.77  4836.5 1701.87  4861.4 1699.17  4926.2 1694.41  4940.6 1694.19
  4947.9 1691.88  4957.1  1687.7  4964.2 1687.51  4964.5 1687.01  4968.3 1687.01
  4968.6 1687.51  4988.8 1688.03  4991.2 1688.56  5000.4 1693.12  5006.7  1693.7
  5109.6 1694.64  5137.2 1696.15  5181.2 1700.81  5202.7 1706.11  5259.4  1726.7
  5275.1 1733.94  5285.1 1740.09  5308.6 1752.74  5338.8 1766.08  5353.3 1771.44
  5392.5 1784.18  5409.2 1787.79    5426 1789.95  5442.8  1794.4  5452.4 1799.63
#Mann= 4 ,-1 , 0
    4799    .035       0  4964.2     .05       0  4968.6     .07       0
  5202.7      .1       0
Bank Sta=4964.2,4968.6
XS Rating Curve= 0 ,0
Exp/Cntr=0.3,0.1

Type RM Length L Ch R = 1 ,10098   ,445,445,445
BEGIN DESCRIPTION:
Cow Creek 21.0
END DESCRIPTION:
XS GIS Cut Line= 3
      1924175.03     13888024.97        1924575.       13887625.
      1924925.03     13887224.96
#Sta/Elev= 30
  4434.8 1710.04  4482.5 1701.55  4508.9 1694.96  4585.2 1689.01    4638 1687.32
  4914.5 1687.42  4958.6 1687.09  5003.4 1683.77  5003.7 1683.27  5007.8 1683.77
  5022.6 1687.24  5066.5 1691.73  5086.4 1697.33    5105 1699.96  5118.3 1705.59
  5142.2 1712.02  5242.5 1736.86  5269.8 1745.76  5280.5 1747.12  5373.7 1775.68
  5397.4 1780.35  5417.3 1787.74  5427.1 1789.48  5447.5  1793.7  5461.1 1798.89
  5471.8  1805.7  5488.5 1811.05    5513 1821.89    5529 1825.48    5532 1826.39
#Mann= 10 ,-1 , 0
  4434.8    .035       0  4482.5     .07       0  4508.9    .035       0
  4914.5     .07       0  5003.4     .05       0  5007.8     .07       0
    5105      .1       0  5373.7     .07       0  5427.1      .1       0
    5529     .07       0
#XS Ineff= 2 , 0
         4782.09 1688.28
Permanent Ineff=
       F       F
Bank Sta=5003.4,5007.8
XS Rating Curve= 0 ,0
Exp/Cntr=0.3,0.1

Type RM Length L Ch R = 1 ,9653    ,484,484,484
BEGIN DESCRIPTION:
Cow Creek 20.0
END DESCRIPTION:
XS GIS Cut Line= 3
      1924524.99     13888325.02        1924875.       13887925.
      1924974.99     13887575.03
#Sta/Elev= 30
  4472.9 1704.47  4536.3  1699.9  4580.7 1689.73    4624 1684.68  4707.7 1679.39
  4736.3 1681.52  4770.7 1681.67  4809.2 1682.29  4859.2 1680.98  4897.5 1681.94
  4933.6  1682.5  4954.9 1681.48  4976.6 1672.14  4976.9 1671.64    4981 1672.14
  4991.4 1674.98  4995.9 1680.26  5000.5 1683.38    5011 1683.26  5043.6 1685.92
  5118.5 1694.42  5162.2 1697.87  5183.3 1700.61  5224.6 1707.84  5237.1 1711.29
  5274.5 1717.41  5287.6 1720.76  5333.7 1729.67  5352.5 1731.24  5368.4 1734.54
#Mann= 5 ,-1 , 0
  4472.9     .07       0  4770.7    .035       0  4897.5     .07       0
  4976.6     .05       0    4981     .07       0
Bank Sta=4976.6,4981
XS Rating Curve= 0 ,0
Exp/Cntr=0.3,0.1

Type RM Length L Ch R = 1 ,9169    ,444,444,444
BEGIN DESCRIPTION:
Cow Creek 19.0
END DESCRIPTION:
XS GIS Cut Line= 3
      1925024.98     13888425.05        1925075.       13888275.
        1925225.       13887475.
#Sta/Elev= 30
  4841.5 1690.42  4845.3  1690.1  4870.5 1687.94  4905.5 1681.43  4930.2 1677.94
  4946.8 1672.49  4966.5 1671.91  4966.8 1671.41    4971 1671.91  4986.8  1673.5
  5070.6 1673.84  5120.8 1676.91  5229.3 1678.53  5305.6 1678.27  5363.6 1681.05
  5445.8 1691.89  5464.3 1691.69  5488.7  1693.9  5513.4 1700.62  5531.5 1703.11
  5586.4 1706.81  5609.6 1708.78  5635.3 1712.46  5644.9 1712.49  5671.9 1716.97
  5682.9 1719.69  5714.6 1727.42  5778.7  1735.7  5813.4 1743.59  5813.6  1743.6
#Mann= 8 ,-1 , 0
  4841.5    .035       0  4845.3     .07       0  4966.5     .05       0
    4971     .07       0  4986.8    .035       0  5120.8     .07       0
  5682.9      .1       0  5813.4     .07       0
Bank Sta=4966.5,4971
XS Rating Curve= 0 ,0
Exp/Cntr=0.3,0.1

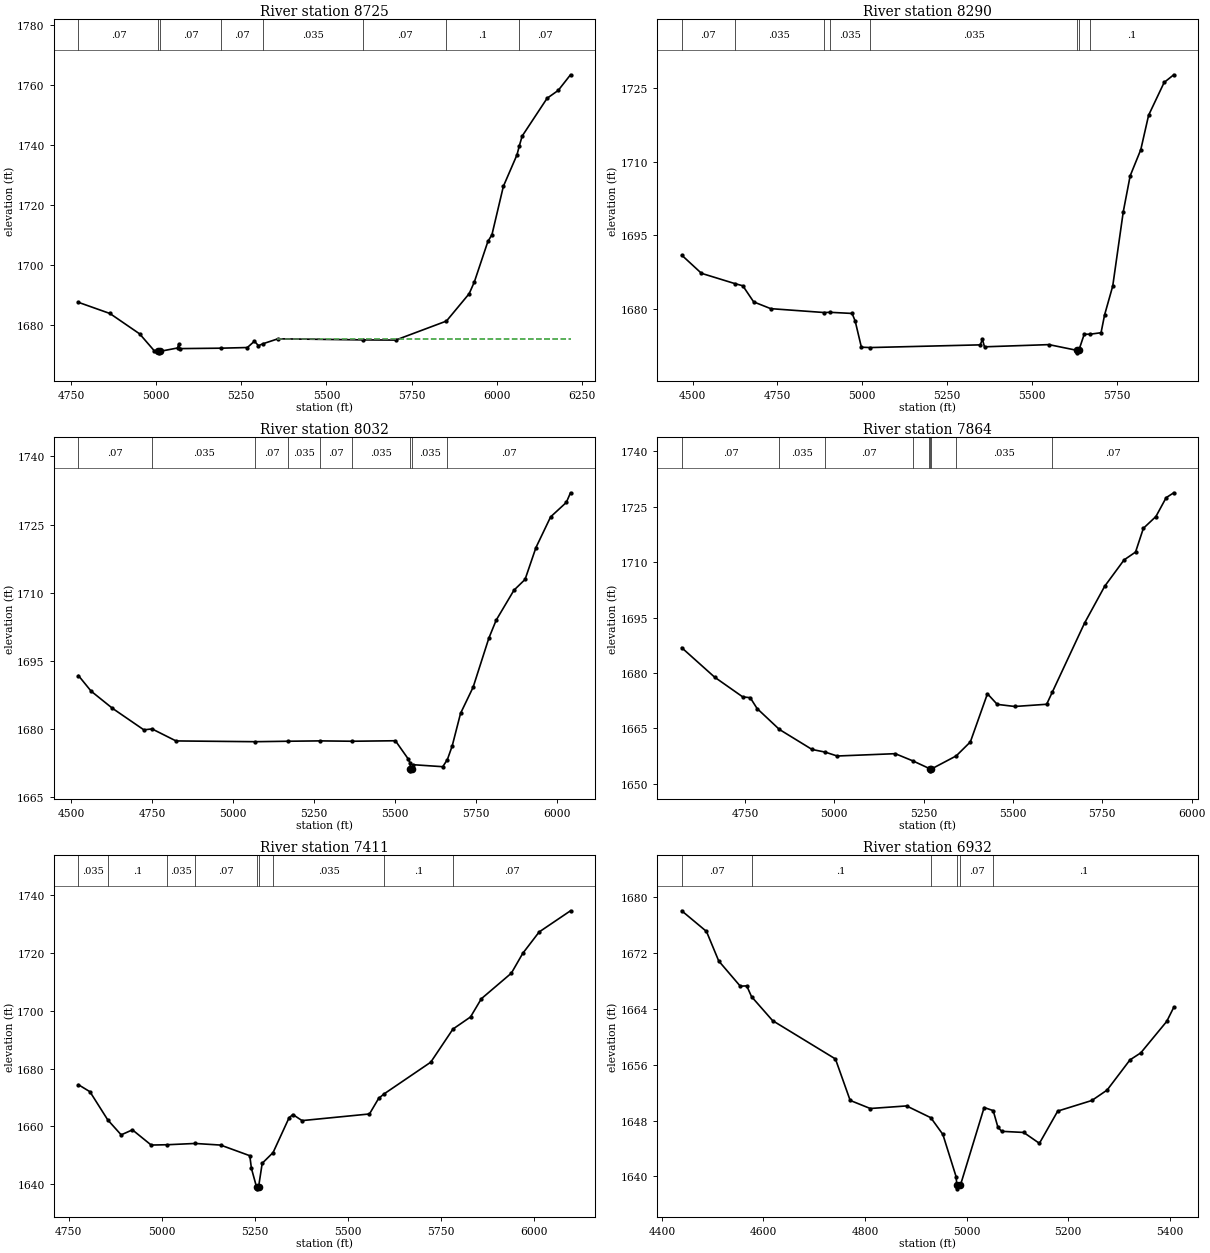
Type RM Length L Ch R = 1 ,8725    ,435,435,435
BEGIN DESCRIPTION:
Cow Creek 18.0
END DESCRIPTION:
XS GIS Cut Line= 4
        1925225.       13888625.        1925425.       13888525.
      1925440.33      13887810.7      1925349.92     13887312.71
#Sta/Elev= 30
  4772.1  1687.6  4864.4 1683.89  4951.6 1677.11  4995.2  1671.4  5006.9 1671.29
  5007.3 1670.79  5011.5 1671.29  5063.2 1672.41  5066.2  1673.7  5069.4  1672.2
  5190.7 1672.34  5267.9 1672.56  5288.5 1674.66  5300.5 1673.17  5313.2  1673.8
  5357.5 1675.46  5608.2  1675.1  5703.3 1675.04  5852.2 1681.37  5918.9 1690.48
  5934.1  1694.4  5973.8 1707.86  5985.7  1710.1  6019.3 1726.23  6059.2 1736.69
  6065.9 1739.61  6074.4 1742.94  6147.6 1755.53  6180.2 1758.14  6216.3 1763.35
#Mann= 8 ,-1 , 0
  4772.1     .07       0  5006.9     .05       0  5011.5     .07       0
  5190.7     .07       0  5313.2    .035       0  5608.2     .07       0
  5852.2      .1       0  6065.9     .07       0
#XS Ineff= 2 , 0
                          5355.9         1675.54
Permanent Ineff=
       F       F
Bank Sta=5006.9,5011.5
XS Rating Curve= 0 ,0
Exp/Cntr=0.3,0.1

Type RM Length L Ch R = 1 ,8290    ,258,258,258
BEGIN DESCRIPTION:
Cow Creek 17.0
END DESCRIPTION:
XS GIS Cut Line= 3
      1925474.99     13889025.01        1925825.       13888625.
        1926625.       13888175.
#Sta/Elev= 30
    4468 1690.92  4526.2  1687.2  4624.1 1685.11  4648.1 1684.65    4680 1681.36
  4730.3 1679.98  4887.1 1679.19  4905.7 1679.23    4970    1679  4979.1 1677.43
  4997.3  1672.1  5023.9 1672.03  5347.3 1672.58  5353.8  1673.7    5360 1672.18
  5549.7 1672.63  5632.9 1671.45  5633.2 1670.95  5637.8 1671.45  5653.7 1674.75
  5671.3 1674.76  5703.3 1675.06  5713.6 1678.67  5737.7  1684.6  5768.7 1699.77
    5789 1707.11  5820.3 1712.46  5843.4 1719.51  5889.2 1726.21  5917.4 1727.77
#Mann= 8 ,-1 , 0
    4468     .07       0  4624.1    .035       0  4887.1     .07       0
  4905.7    .035       0  5023.9    .035       0  5632.9    .035       0
  5637.8    .035       0  5671.3      .1       0
Bank Sta=5632.9,5637.8
XS Rating Curve= 0 ,0
Exp/Cntr=0.3,0.1

Type RM Length L Ch R = 1 ,8032    ,168,168,168
BEGIN DESCRIPTION:
Cow Creek 16.1
END DESCRIPTION:
XS GIS Cut Line= 5
      1925496.88     13889061.65      1925674.86     13888870.65
      1926035.11     13888814.22      1926516.88     13888744.78
       1926894.5     13888592.86
#Sta/Elev= 30
  4522.9 1691.77    4562 1688.35    4628 1684.57  4724.8 1679.84  4750.2 1680.04
  4824.1  1677.4  5068.7 1677.23    5169 1677.33    5269 1677.41    5369 1677.33
  5501.7 1677.44  5541.1 1673.45  5547.3 1672.49  5547.7 1671.32  5548.1 1670.82
  5552.6 1671.32  5556.2 1672.17  5647.9 1671.73  5662.2  1673.3    5677 1676.28
  5702.9 1683.47  5741.7 1689.22  5790.2    1700  5812.9 1703.97  5867.8 1710.56
  5902.1 1712.93  5935.7 1719.94    5981 1726.69  6029.5 1729.87  6042.4 1731.99
#Mann= 9 ,-1 , 0
  4522.9     .07       0  4750.2    .035       0  5068.7     .07       0
    5169    .035       0    5269     .07       0    5369    .035       0
  5547.7    .035       0  5552.6    .035       0  5662.2     .07       0
Bank Sta=5547.7,5552.6
XS Rating Curve= 0 ,0
Exp/Cntr=0.3,0.1

Type RM Length L Ch R = 1 ,7864    ,453,453,453
BEGIN DESCRIPTION:
Cow Creek 16.0
END DESCRIPTION:
XS GIS Cut Line= 3
        1925575.       13889125.        1925975.       13888975.
      1926869.57     13888655.54
#Sta/Elev= 30
  4572.8 1686.85  4665.2 1678.86  4743.7 1673.54  4764.6 1673.33  4783.8  1670.4
  4846.1 1664.75  4937.6 1659.33  4974.5 1658.61    5008 1657.56  5170.5 1658.19
  5219.8 1656.24  5266.1 1654.17  5266.8 1654.05  5267.1 1653.55  5271.7 1654.05
  5341.1 1657.59  5380.7 1661.37  5428.5 1674.39  5455.9 1671.52    5505 1670.95
  5594.2 1671.55  5609.9  1674.8  5700.3  1693.5  5756.6 1703.45  5810.8 1710.57
    5843  1712.7  5864.9 1719.12    5900 1722.31  5928.6  1727.4  5949.9 1728.73
#Mann= 9 ,-1 , 0
  4572.8     .07       0  4846.1    .035       0  4974.5     .07       0
  5219.8    .035       0  5266.1     .07       0  5266.8     .05       0
  5271.7     .07       0  5341.1    .035       0  5609.9     .07       0
Bank Sta=5266.8,5271.7
XS Rating Curve= 0 ,0
Exp/Cntr=0.3,0.1

Type RM Length L Ch R = 1 ,7411    ,479,479,479
BEGIN DESCRIPTION:
Cow Creek 15.0
END DESCRIPTION:
XS GIS Cut Line= 3
      1925925.03     13889474.98        1926125.       13889375.
      1926925.03     13888624.97
#Sta/Elev= 30
  4776.7 1674.43  4807.5 1672.01  4855.3 1662.26  4891.3 1657.08  4921.5 1658.81
  4971.8 1653.55  5015.5 1653.66  5089.7  1654.1  5158.1 1653.54  5236.4 1649.86
  5240.8 1645.46  5254.8 1638.89  5255.2 1638.39  5259.8 1638.89  5269.7 1647.23
  5298.9 1650.95  5341.7 1662.97  5351.9 1664.12  5376.6 1662.01  5557.5 1664.31
  5582.2 1669.72    5597 1671.28    5722 1682.24  5781.5  1693.7  5828.6 1697.89
  5857.7  1704.2  5938.2 1713.05  5968.9 1719.93  6012.8 1727.32  6096.9 1734.65
#Mann= 9 ,-1 , 0
  4776.7    .035       0  4855.3      .1       0  5015.5    .035       0
  5089.7     .07       0  5254.8     .05       0  5259.8     .07       0
  5298.9    .035       0    5597      .1       0  5781.5     .07       0
Bank Sta=5254.8,5259.8
XS Rating Curve= 0 ,0
Exp/Cntr=0.3,0.1

Type RM Length L Ch R = 1 ,6932    ,467,467,467
BEGIN DESCRIPTION:
Cow Creek 14.0
END DESCRIPTION:
XS GIS Cut Line= 3
      1926074.99     13890025.01        1926475.       13889625.
      1926874.99       13889575.
#Sta/Elev= 30
  4439.1 1678.06  4487.9  1675.1    4512 1670.87  4554.4 1667.26  4567.2  1667.3
  4576.6 1665.76  4618.1 1662.32  4741.8 1656.83  4770.8 1650.89  4810.4 1649.73
  4881.8  1650.1  4929.6 1648.41  4953.3 1646.02  4979.4 1639.96  4980.8 1638.72
  4981.3 1638.22  4987.8 1638.72  5034.6 1649.87  5052.4 1649.43  5061.8 1647.03
  5069.3 1646.46  5112.4  1646.3  5143.4 1644.74  5179.5 1649.36  5246.7 1650.88
  5276.7 1652.37  5321.8  1656.7    5343  1657.7  5394.1 1662.21  5407.9 1664.22
#Mann= 6 ,-1 , 0
  4439.1     .07       0  4576.6      .1       0  4929.6     .07       0
  4980.8     .05       0  4987.8     .07       0  5052.4      .1       0
Bank Sta=4980.8,4987.8
XS Rating Curve= 0 ,0
Exp/Cntr=0.3,0.1

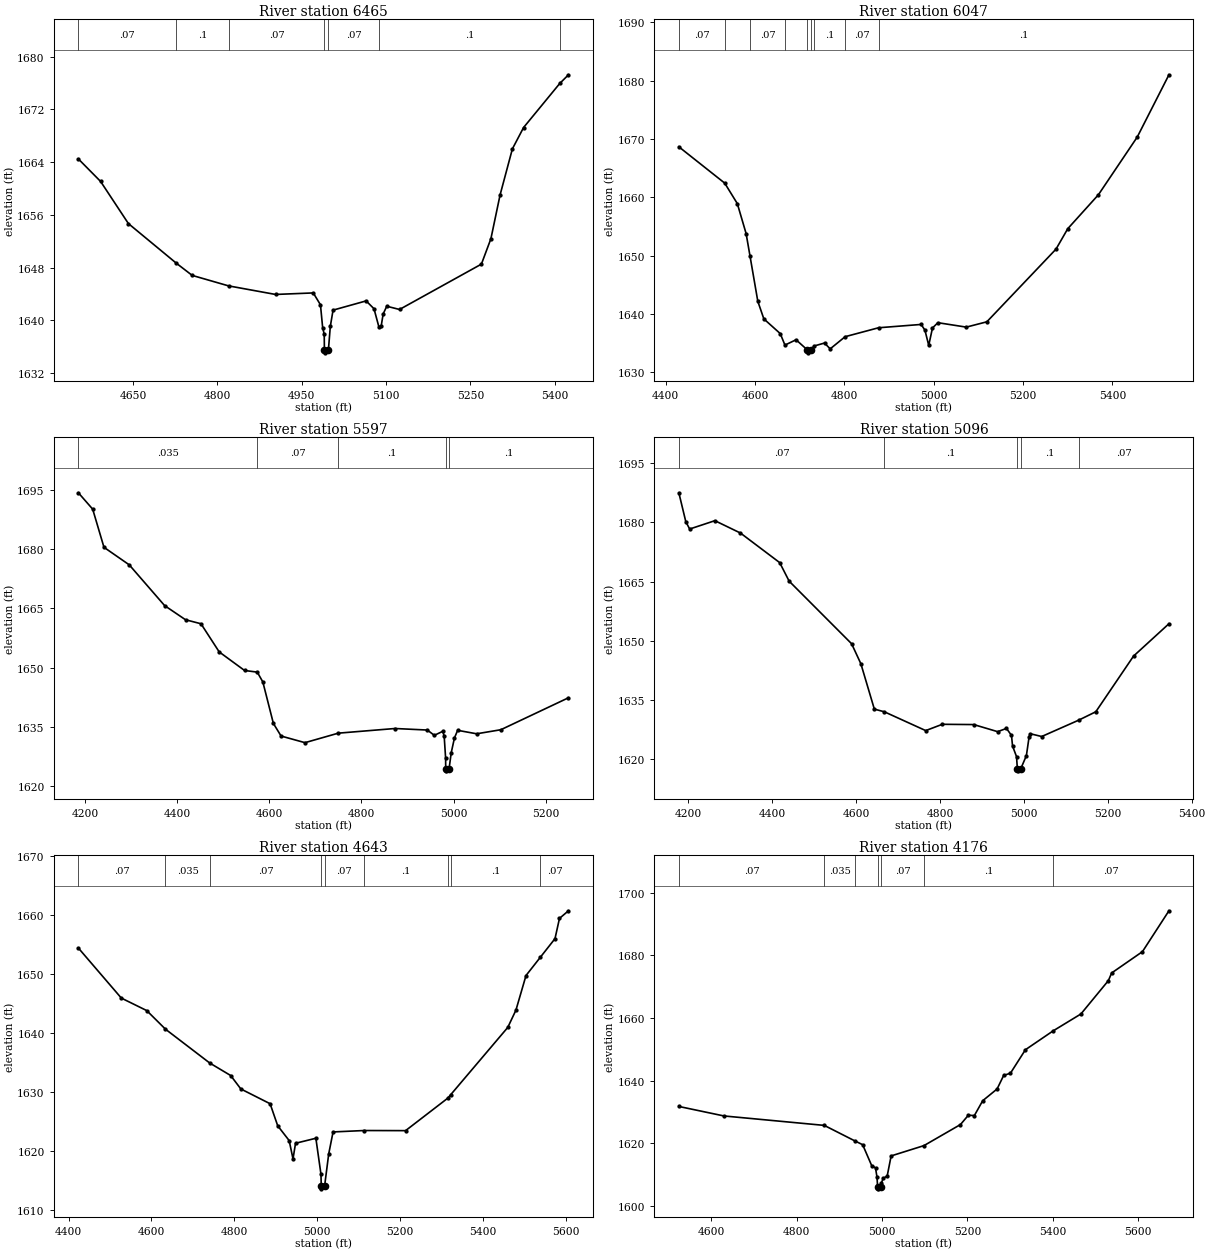
Type RM Length L Ch R = 1 ,6465    ,418,418,418
BEGIN DESCRIPTION:
Cow Creek 13.0
END DESCRIPTION:
XS GIS Cut Line= 3
      1926274.98     13890225.01        1926675.       13890025.
        1926975.       13889725.
#Sta/Elev= 30
    4553 1664.49  4592.6 1661.07    4642 1654.68  4727.5 1648.65  4755.4 1646.82
  4820.1 1645.23  4903.6 1643.93  4970.7 1644.16  4983.5 1642.36  4987.4  1638.9
  4990.2 1637.88  4990.5 1635.57    4991 1635.07  4997.7 1635.57    5001 1639.07
  5005.9 1641.55  5064.7 1642.95  5078.7 1641.76  5087.6 1638.94  5091.5 1639.14
    5095 1640.97  5101.4 1642.14  5124.1 1641.65  5269.7 1648.53  5286.6 1652.39
  5302.9 1659.03  5324.8 1666.02  5344.7 1669.26    5409 1675.94  5424.5 1677.26
#Mann= 7 ,-1 , 0
    4553     .07       0  4727.5      .1       0  4820.1     .07       0
  4990.5     .05       0  4997.7     .07       0  5087.6      .1       0
    5409     .07       0
Bank Sta=4990.5,4997.7
XS Rating Curve= 0 ,0
Exp/Cntr=0.3,0.1

Type RM Length L Ch R = 1 ,6047    ,450,450,450
BEGIN DESCRIPTION:
Cow Creek 12.0
END DESCRIPTION:
XS GIS Cut Line= 3
      1926474.99     13890775.01        1926875.       13890375.
      1927274.99     13890025.01
#Sta/Elev= 30
  4429.4 1668.65  4532.1 1662.42  4560.3 1658.91    4580 1653.77  4588.6 1649.97
  4606.2 1642.15  4619.7 1639.14  4656.4 1636.62  4666.9 1634.65  4691.8 1635.56
  4717.1 1633.82  4717.6 1633.32  4724.4 1633.82  4732.5  1634.5  4755.5    1635
  4768.2    1634  4801.7 1636.09  4876.5 1637.62  4971.8 1638.19  4980.3 1637.21
  4988.8  1634.6  4997.2 1637.58  5009.3 1638.49  5072.9 1637.73  5118.9 1638.64
  5273.8 1651.11  5300.1 1654.61  5368.6 1660.42  5455.6 1670.32  5526.6    1681
#Mann= 9 ,-1 , 0
  4429.4     .07       0  4532.1    .035       0  4588.6     .07       0
  4666.9     .07       0  4717.1     .05       0  4724.4     .07       0
  4732.5      .1       0  4801.7     .07       0  4876.5      .1       0
Bank Sta=4717.1,4724.4
XS Rating Curve= 0 ,0
Exp/Cntr=0.3,0.1

Type RM Length L Ch R = 1 ,5597    ,501,501,501
BEGIN DESCRIPTION:
Cow Creek 11.0
END DESCRIPTION:
XS GIS Cut Line= 3
      1926224.95     13890925.01        1927025.       13890775.
      1927225.01     13890624.99
#Sta/Elev= 30
  4185.5 1694.32  4216.6 1690.17  4241.1  1680.5    4296 1676.05  4372.8 1665.72
  4418.1 1662.14  4451.7 1661.12  4491.3 1653.98  4546.3 1649.28  4573.9 1648.86
    4586 1646.37  4608.9 1635.85  4625.6 1632.66  4677.5 1630.98  4749.8 1633.39
  4872.9 1634.57  4943.1 1634.18  4958.3 1632.84  4976.6 1633.86  4979.7 1632.61
  4982.8 1627.05    4983 1624.34  4983.5 1623.84  4990.3 1624.34    4995 1628.44
    5002 1632.19  5008.9 1634.11  5050.2 1633.23  5102.7 1634.26  5249.5 1642.36
#Mann= 5 ,-1 , 0
  4185.5    .035       0  4573.9     .07       0  4749.8      .1       0
    4983     .05       0  4990.3      .1       0
Bank Sta=4983,4990.3
XS Rating Curve= 0 ,0
Exp/Cntr=0.3,0.1

Type RM Length L Ch R = 1 ,5096    ,453,453,453
BEGIN DESCRIPTION:
Cow Creek 10.0
END DESCRIPTION:
XS GIS Cut Line= 4
      1926238.96     13891104.56       1926669.8       13891275.
        1927025.       13891275.      1927374.97       13891275.
#Sta/Elev= 30
  4177.2 1687.54  4193.8  1680.2    4203 1678.34  4263.1 1680.46  4324.1 1677.32
  4417.6 1669.82  4440.2 1665.11  4589.1 1649.23  4611.2 1644.15  4643.3 1632.64
    4667 1631.97  4765.8 1627.19  4805.3 1628.79  4880.3 1628.72  4937.3 1626.92
  4958.3 1627.75  4970.3 1625.96  4972.8 1623.29  4982.3 1620.58  4984.3 1617.48
  4984.8 1616.98  4992.3 1617.48  5005.8 1620.84  5012.3 1625.62  5015.3 1626.39
  5042.3 1625.69  5130.1 1629.82  5171.3 1631.97  5261.3  1646.1  5345.7 1654.31
#Mann= 5 ,-1 , 0
  4177.2     .07       0    4667      .1       0  4984.3     .05       0
  4992.3      .1       0  5130.1     .07       0
Bank Sta=4984.3,4992.3
XS Rating Curve= 0 ,0
Exp/Cntr=0.3,0.1

Type RM Length L Ch R = 1 ,4643    ,467,467,467
BEGIN DESCRIPTION:
Cow Creek 9.0
END DESCRIPTION:
XS GIS Cut Line= 3
      1926511.23     13891797.62        1927075.       13891675.
       1927594.4     13891362.32
#Sta/Elev= 30
  4423.5 1654.39  4527.2 1645.91  4588.6 1643.79  4633.8 1640.64  4740.8  1634.9
  4791.2 1632.79  4815.8 1630.51  4886.4 1628.01  4904.8 1624.27  4932.4 1621.77
  4941.7 1618.67  4947.8 1621.31  4996.9 1622.16  5009.2 1616.06  5009.9 1614.09
  5010.4 1613.59    5018 1614.09  5027.9 1619.51  5038.4 1623.23  5113.4 1623.47
  5213.5 1623.45  5315.3 1628.95  5322.3 1629.53  5460.2 1640.94  5479.9 1643.87
  5504.2 1649.73  5539.1 1652.85  5574.2 1655.98    5585 1659.41  5606.7  1660.7
#Mann= 9 ,-1 , 0
  4423.5     .07       0  4633.8    .035       0  4740.8     .07       0
  5009.9     .05       0    5018     .07       0  5113.4      .1       0
  5315.3     .07       0  5322.3      .1       0  5539.1     .07       0
Bank Sta=5009.9,5018
XS Rating Curve= 0 ,0
Exp/Cntr=0.3,0.1

Type RM Length L Ch R = 1 ,4176    ,454,454,454
BEGIN DESCRIPTION:
Cow Creek 8.0
END DESCRIPTION:
XS GIS Cut Line= 3
      1926900.22     13892010.17        1927375.       13891975.
      1928032.34     13891836.26
#Sta/Elev= 30
  4524.2 1631.81  4629.8 1628.78  4864.8 1625.77  4937.2 1620.77  4954.7 1619.61
  4975.8 1612.96  4984.8  1612.2  4988.4  1609.2  4989.7 1606.03  4990.2 1605.53
  4997.9 1606.03  4998.2 1607.27  5002.9 1608.91  5012.1 1609.58  5021.4 1616.03
  5098.3 1619.32  5183.8 1626.04  5202.2    1629  5216.4 1628.92  5235.9 1633.64
  5269.6 1637.39    5285 1641.71  5300.9 1642.42  5335.9  1649.9  5400.5 1655.89
  5465.9 1661.31  5530.2 1671.95  5537.9 1674.39    5610 1681.19  5672.1 1694.23
#Mann= 7 ,-1 , 0
  4524.2     .07       0  4864.8    .035       0  4937.2     .07       0
  4989.7     .05       0  4997.9     .07       0  5098.3      .1       0
  5400.5     .07       0
Bank Sta=4989.7,4997.9
XS Rating Curve= 0 ,0
Exp/Cntr=0.3,0.1

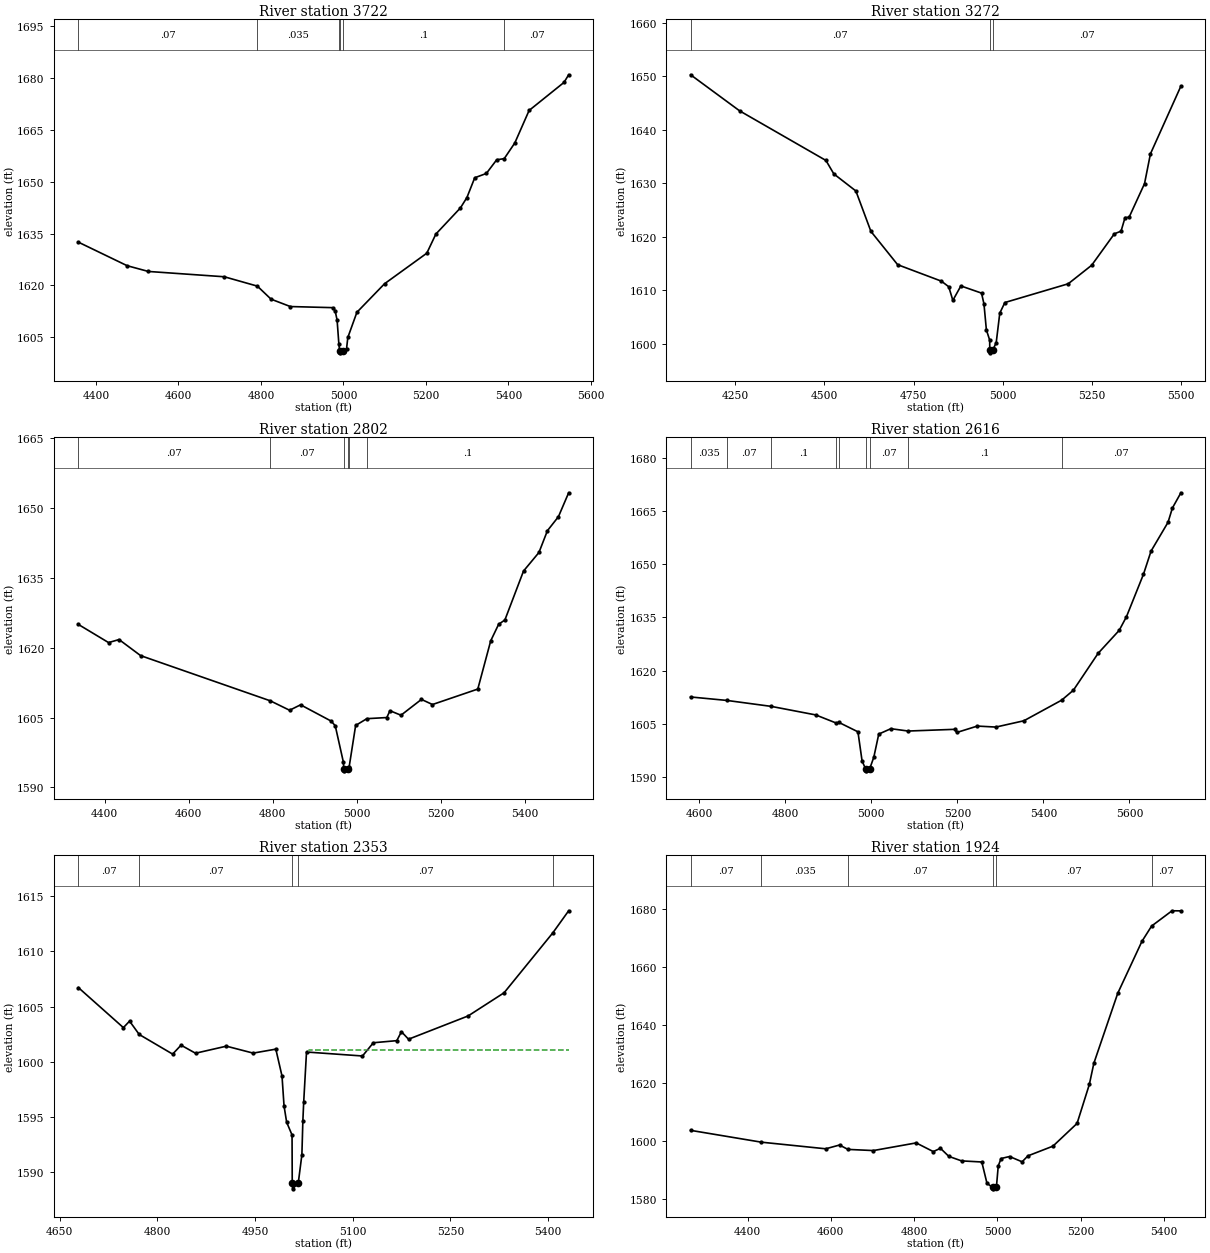
Type RM Length L Ch R = 1 ,3722    ,450,450,450
BEGIN DESCRIPTION:
Cow Creek 7.0
END DESCRIPTION:
XS GIS Cut Line= 3
      1926890.97     13892303.98        1927525.       13892375.
      1928051.27     13892213.45
#Sta/Elev= 30
  4357.4 1632.51  4475.7 1625.69    4527 1624.03  4711.2 1622.49  4791.3 1619.78
  4824.4 1616.01  4871.2 1613.87  4973.8 1613.55  4979.8 1612.66  4984.6 1609.94
  4988.9 1602.97  4990.8 1600.97  4991.3 1600.47    4999 1600.97  5007.5 1601.69
  5010.6 1604.92  5032.6 1612.21  5099.6 1620.47    5202 1629.31    5224 1634.85
  5283.6 1642.43  5299.3 1645.43  5318.2 1651.15  5346.4  1652.4  5371.5 1656.36
  5389.7 1656.68  5415.4 1661.23    5450 1670.63  5534.7 1678.76  5545.9 1680.96
#Mann= 6 ,-1 , 0
  4357.4     .07       0  4791.3    .035       0  4988.9      .1       0
  4990.8     .05       0    4999      .1       0  5389.7     .07       0
Bank Sta=4990.8,4999
XS Rating Curve= 0 ,0
Exp/Cntr=0.3,0.1

Type RM Length L Ch R = 1 ,3272    ,470,470,470
BEGIN DESCRIPTION:
Cow Creek 6.0
END DESCRIPTION:
XS GIS Cut Line= 3
       1926704.6     13893192.48        1927475.       13892775.
      1927874.96     13892475.03
#Sta/Elev= 30
  4124.3 1650.28  4261.9 1643.54  4504.2 1634.27  4526.3 1631.76  4588.2 1628.57
  4630.4 1621.02  4705.4  1614.8  4828.3 1611.72  4848.8 1610.68  4860.4 1608.13
  4882.9 1610.83  4940.9 1609.49  4947.7 1607.47  4954.5 1602.62  4963.8  1600.7
    4964 1598.83  4964.5 1598.33  4972.3 1598.83  4982.1 1600.24  4992.1 1605.74
  5006.4 1607.73  5184.2 1611.23    5250 1614.69  5313.7 1620.57  5332.5 1621.06
  5343.7  1623.6    5355 1623.65  5398.4 1629.94    5415 1635.51  5500.5 1648.16
#Mann= 3 ,-1 , 0
  4124.3     .07       0    4964     .05       0  4972.3     .07       0
Bank Sta=4964,4972.3
XS Rating Curve= 0 ,0
Exp/Cntr=0.3,0.1

Type RM Length L Ch R = 1 ,2802    ,186,186,186
BEGIN DESCRIPTION:
Cow Creek 5.0
END DESCRIPTION:
XS GIS Cut Line= 3
      1927149.97     13893587.35        1927675.       13893175.
        1928075.       13892875.
#Sta/Elev= 30
  4337.2 1625.04  4409.1 1621.14  4434.1 1621.79  4485.4 1618.34  4794.4 1608.62
  4840.2  1606.6  4866.4 1607.77  4939.4 1604.26    4949 1603.25  4968.4 1595.42
  4969.2 1594.08  4969.7 1593.58  4978.2 1594.08  4982.1 1594.44  4997.5 1603.33
  5024.2 1604.79  5071.7 1605.03  5079.2  1606.5  5105.5 1605.53  5154.2 1608.93
  5180.5 1607.83  5288.4 1611.15  5319.2 1621.52    5338 1625.06    5353 1626.01
  5397.3 1636.51  5434.1 1640.51  5454.2 1645.18  5480.5  1648.2  5504.8 1653.33
#Mann= 6 ,-1 , 0
  4337.2     .07       0  4794.4     .07       0  4969.2     .05       0
  4978.2     .07       0  4982.1     .07       0  5024.2      .1       0
Bank Sta=4969.2,4978.2
XS Rating Curve= 0 ,0
Exp/Cntr=0.3,0.1

Type RM Length L Ch R = 1 ,2616    ,263,263,263
BEGIN DESCRIPTION:
Mapping XS f89d4818
END DESCRIPTION:
XS GIS Cut Line= 3
      1927415.17     13893606.83      1927895.56     13893219.09
        1928277.     13892862.07
#Sta/Elev= 30
  4579.8 1612.53  4664.3 1611.55  4767.3 1609.87  4870.7 1607.46    4918 1605.18
  4924.3 1605.36  4968.8 1602.69  4978.4 1594.48  4986.7 1592.17  4987.2 1591.67
  4995.9 1592.17  5005.7 1595.52  5017.2 1602.05  5045.3 1603.57  5085.5 1602.91
  5193.3 1603.39  5198.5  1602.5  5246.3 1604.31  5289.5 1604.03  5354.6 1605.81
  5442.4 1611.63  5469.7 1614.44  5527.2 1624.86  5576.1 1631.33  5593.1 1635.21
  5632.6 1647.19  5650.2 1653.72  5689.7 1661.86  5699.8 1665.88  5719.6 1670.19
#Mann= 9 ,-1 , 0
  4579.8    .035       0  4664.3     .07       0  4767.3      .1       0
    4918    .035       0  4924.3     .07       0  4986.7     .05       0
  4995.9     .07       0  5085.5      .1       0  5442.4     .07       0
Bank Sta=4986.7,4995.9
XS Rating Curve= 0 ,0
Exp/Cntr=0.3,0.1

Type RM Length L Ch R = 1 ,2353    ,429,429,429
BEGIN DESCRIPTION:
Cow Creek 4.0
END DESCRIPTION:
XS GIS Cut Line= 3
      1927675.01       13893525.        1927975.       13893425.
       1928277.2     13893110.18
#Sta/Elev= 30
  4678.8 1606.73  4747.9  1603.1  4757.4 1603.69  4772.2 1602.48  4823.5  1600.7
  4836.4 1601.51  4858.6 1600.78    4906 1601.42  4947.1 1600.79  4981.9 1601.15
  4991.4 1598.71  4994.5 1596.01  4998.5 1594.53  5006.8 1593.37  5007.1 1588.99
  5007.6 1588.49  5016.3 1588.99  5021.9 1591.58  5023.4 1594.65  5024.7 1596.37
    5029 1600.89  5114.9 1600.53  5131.6 1601.73  5167.6 1601.92  5174.7 1602.73
  5185.6 1602.05  5277.1 1604.16  5332.3 1606.26  5407.1 1611.69  5431.4 1613.69
#Mann= 5 ,-1 , 0
  4678.8     .07       0  4772.2     .07       0  5007.1     .05       0
  5016.3     .07       0  5407.1     .07       0
#XS Ineff= 2 , 0
                         5032.57         1601.05
Permanent Ineff=
       F       F
Bank Sta=5007.1,5016.3
XS Rating Curve= 0 ,0
Exp/Cntr=0.3,0.1

Type RM Length L Ch R = 1 ,1924    ,190,190,190
BEGIN DESCRIPTION:
Cow Creek 3.1
END DESCRIPTION:
XS GIS Cut Line= 4
      1927599.91     13893787.36      1928157.06      13893748.9
      1928398.23     13893622.22      1928685.23     13893428.58
#Sta/Elev= 30
  4263.4 1603.73  4433.4 1599.65  4587.8 1597.37  4620.9 1598.67  4641.1 1597.16
  4702.1 1596.76  4804.9  1599.4  4846.1  1596.4  4863.1 1597.55  4883.4 1594.75
  4913.9  1593.2  4962.5 1592.82  4974.9 1585.48  4988.2 1584.06  4988.7 1583.56
  4997.5 1584.06    5002 1591.48  5008.8 1594.01  5029.1 1594.71  5059.3 1592.88
  5073.2 1594.93  5133.3 1598.28  5191.2 1606.12  5220.7 1619.58  5231.5 1626.86
  5288.9 1651.01  5346.8 1668.87  5370.2 1674.19  5419.2 1679.45  5440.5 1679.42
#Mann= 6 ,-1 , 0
  4263.4     .07       0  4433.4    .035       0  4641.1     .07       0
  4988.2     .05       0  4997.5     .07       0  5370.2     .07       0
Bank Sta=4988.2,4997.5
XS Rating Curve= 0 ,0
Exp/Cntr=0.3,0.1

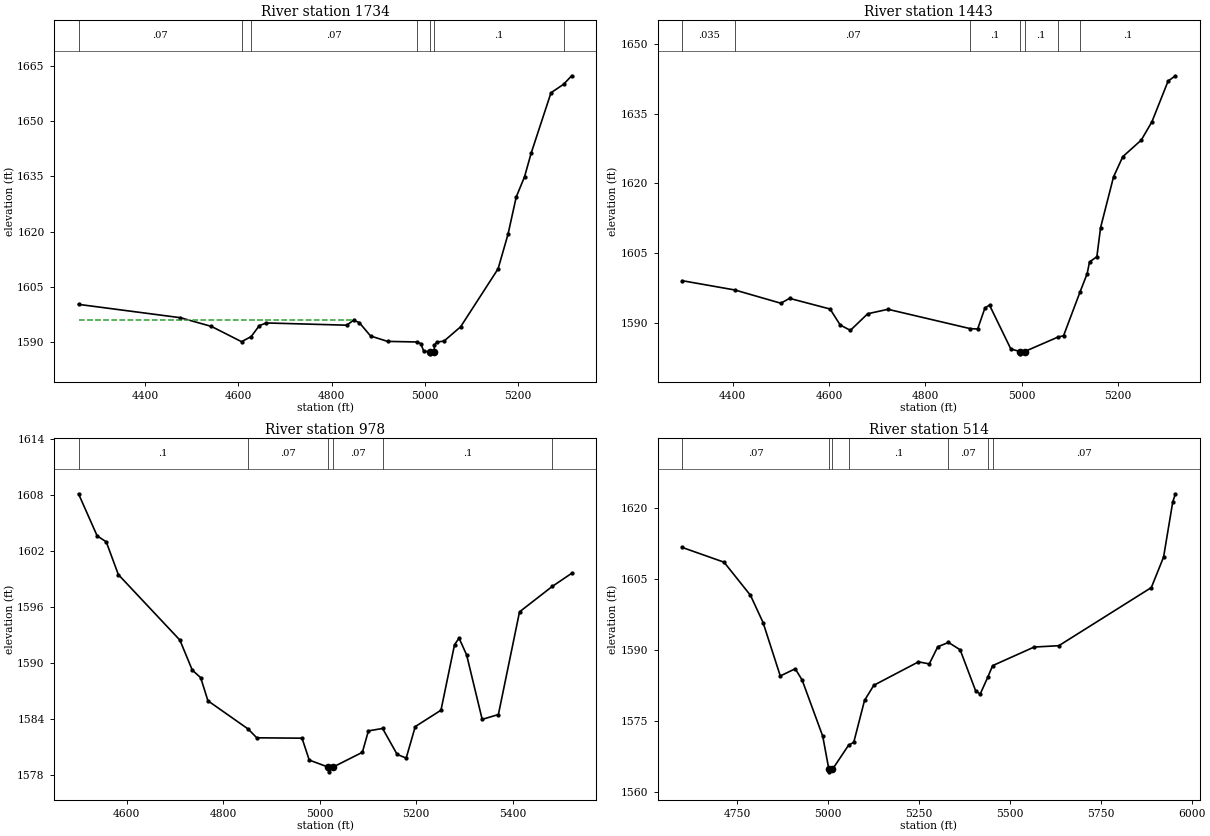
Type RM Length L Ch R = 1 ,1734    ,291,291,291
BEGIN DESCRIPTION:
Mapping XS b767c81a
END DESCRIPTION:
XS GIS Cut Line= 3
      1927691.77     13893941.06      1928352.74     13893858.47
        1928684.     13893649.46
#Sta/Elev= 30
    4257 1600.18  4475.5 1596.55    4542 1594.18  4606.7 1590.02  4627.4 1591.41
  4644.8 1594.39  4659.9 1595.12  4832.2 1594.51  4847.3 1595.87  4859.4  1595.2
  4883.5 1591.57  4919.9  1590.1  4982.7 1589.94  4991.1 1589.51  4997.4 1587.48
  5010.5 1587.21    5011 1586.71  5019.8 1587.21  5020.5 1589.14  5025.8 1589.91
  5041.1 1590.19  5076.7 1594.08    5157 1609.85  5178.3 1619.26    5196 1629.44
  5213.8 1634.93  5227.9 1641.32  5270.5 1657.79  5297.7 1660.12  5314.8 1662.42
#Mann= 7 ,-1 , 0
    4257     .07       0  4606.7    .035       0  4627.4     .07       0
  4982.7      .1       0  5010.5     .05       0  5019.8      .1       0
  5297.7     .07       0
#XS Ineff= 2 , 0
         4845.25 1595.95
Permanent Ineff=
       F       F
Bank Sta=5010.5,5019.8
XS Rating Curve= 0 ,0
Exp/Cntr=0.3,0.1

Type RM Length L Ch R = 1 ,1443    ,465,465,465
BEGIN DESCRIPTION:
Cow Creek 3.0
END DESCRIPTION:
XS GIS Cut Line= 3
      1927722.21     13894032.84        1928425.       13894075.
        1928675.       13893875.
#Sta/Elev= 30
  4295.4 1599.08  4404.5 1597.09  4500.1 1594.24  4518.1 1595.29  4602.3    1593
  4623.3 1589.57  4644.4 1588.41  4680.4 1591.98  4722.5 1592.94  4893.6 1588.78
  4908.8 1588.71  4923.9 1593.22  4933.4 1593.84  4977.8 1584.39  4997.2 1583.87
  4997.7 1583.37  5006.6 1583.87  5075.1 1586.95  5087.2 1587.26  5121.8 1596.76
  5136.3 1600.61  5141.1 1603.12  5156.4 1604.23  5164.1 1610.49    5191 1621.38
  5210.2 1625.73  5248.6 1629.29  5270.8 1633.24  5304.4 1641.99  5319.6 1643.11
#Mann= 7 ,-1 , 0
  4295.4    .035       0  4404.5     .07       0  4893.6      .1       0
  4997.2     .05       0  5006.6      .1       0  5075.1     .07       0
  5121.8      .1       0
Bank Sta=4997.2,5006.6
XS Rating Curve= 0 ,0
Exp/Cntr=0.3,0.1

Type RM Length L Ch R = 1 ,978     ,464,464,464
BEGIN DESCRIPTION:
Cow Creek 2.0
END DESCRIPTION:
XS GIS Cut Line= 3
      1927774.99     13894675.01        1928175.       13894375.
      1928674.97     13894225.01
#Sta/Elev= 30
  4500.1 1608.09  4538.7 1603.59  4557.6 1602.95  4582.6 1599.45  4710.2 1592.44
  4735.9 1589.23  4753.3 1588.42  4768.3 1585.95  4851.4 1582.94  4869.6 1581.99
  4963.3 1581.95  4978.3 1579.61  5017.9 1578.85  5018.4 1578.35  5027.3 1578.85
  5088.4 1580.44  5100.9 1582.73  5130.3 1582.99  5160.4 1580.22  5179.2 1579.82
    5198 1583.19  5251.3 1584.94  5279.4 1591.95  5288.8 1592.65  5304.5 1590.85
  5336.7 1583.96  5370.3 1584.48  5414.1 1595.46  5482.4  1598.2  5522.1 1599.58
#Mann= 6 ,-1 , 0
  4500.1      .1       0  4851.4     .07       0  5017.9     .05       0
  5027.3     .07       0  5130.3      .1       0  5482.4     .07       0
Bank Sta=5017.9,5027.3
XS Rating Curve= 0 ,0
Exp/Cntr=0.3,0.1

Type RM Length L Ch R = 1 ,514     ,0,0,0
BEGIN DESCRIPTION:
Cow Creek 1.0
END DESCRIPTION:
XS GIS Cut Line= 4
      1927847.54     13894949.74        1928225.       13894825.
        1928325.       13894725.      1928903.52     13894146.35
#Sta/Elev= 30
  4598.2 1611.57    4713 1608.46  4785.7 1601.47  4820.4 1595.72  4867.8 1584.43
  4908.9 1585.95  4927.9 1583.58  4984.7  1571.7  5001.6 1564.68  5002.1 1564.18
  5011.2 1564.68  5055.9 1569.82    5070 1570.41  5099.7 1579.27  5125.2 1582.46
  5248.2 1587.41  5277.9 1586.98  5301.3  1590.6  5330.7 1591.51  5362.8 1589.96
  5405.3 1581.33    5418  1580.6  5439.1 1584.21  5452.2 1586.61  5566.5 1590.54
  5634.4 1590.82    5889  1603.1  5922.7 1609.53  5948.1 1621.24  5955.4 1622.91
#Mann= 7 ,-1 , 0
  4598.2     .07       0  5001.6     .05       0  5011.2     .07       0
  5055.9      .1       0  5330.7     .07       0  5439.1      .1       0
  5452.2     .07       0
Bank Sta=5001.6,5011.2
XS Rating Curve= 0 ,0
Exp/Cntr=0.3,0.1

Chan Stop Cuts=-1
Use User Specified Reach Order=0
Composite Channel Slope=5