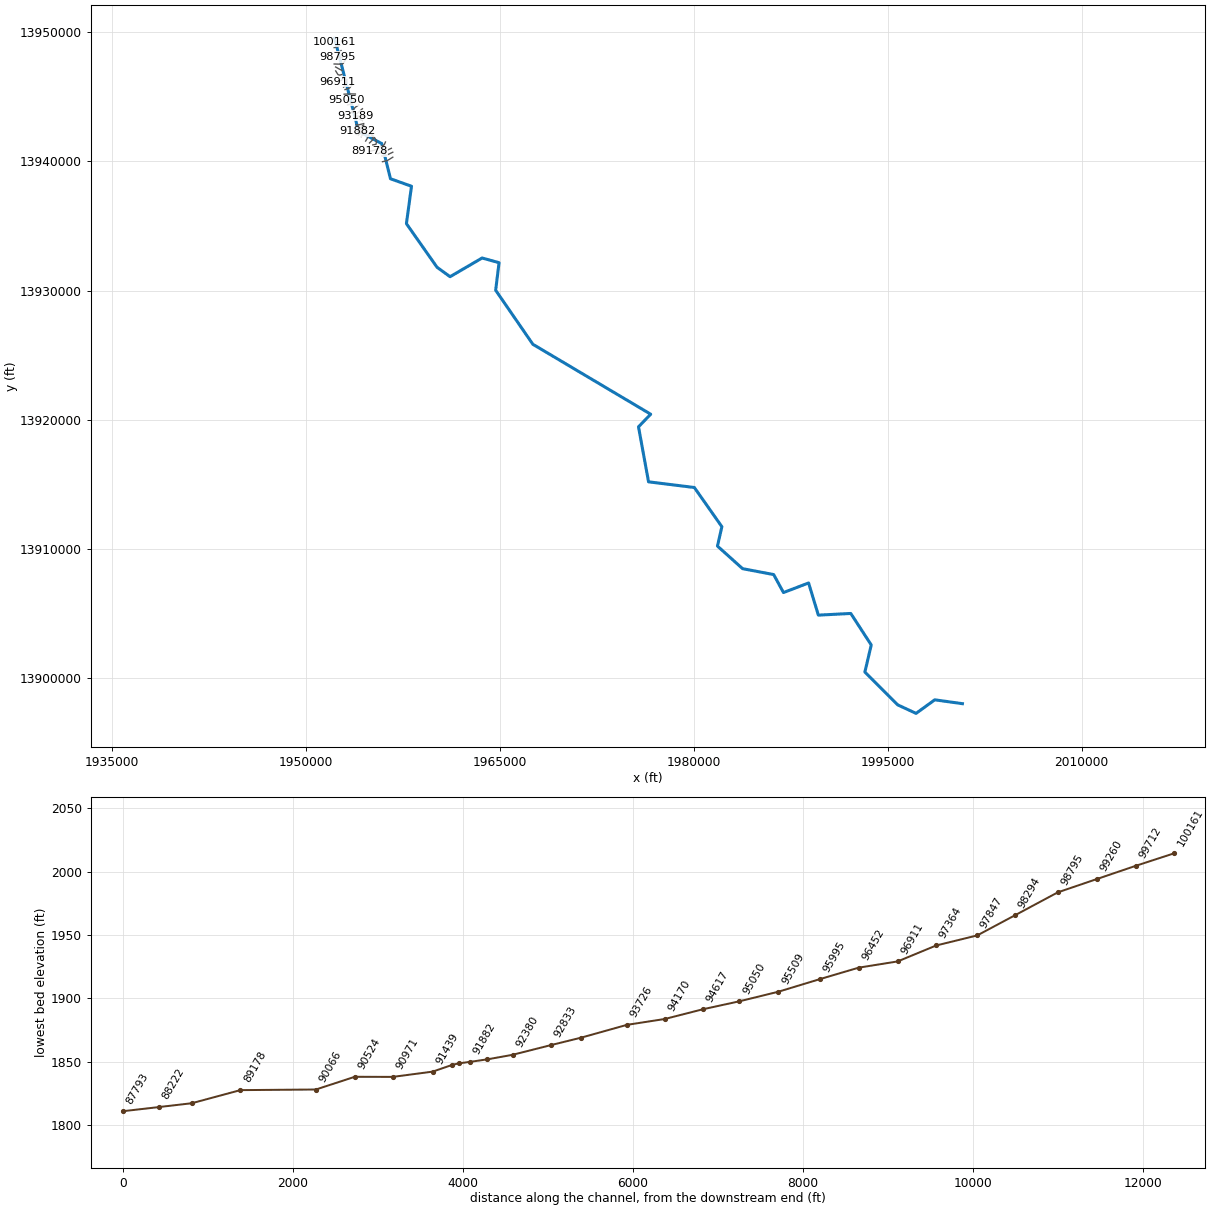
--- Cypress Creek.prj (project) ---

Proj Title=Cypress Creek Base Level Engineering
Current Plan=p01
Default Exp/Contr=0.3,0.1
English Units
Geom File=g01
Flow File=f01
Plan File=p01
Y Axis Title=Elevation
X Axis Title(PF)=Main Channel Distance
X Axis Title(XS)=Station
BEGIN DESCRIPTION:
Cypress Creek
END DESCRIPTION:
DSS Export Rating Curves= 0
DSS Export Rating Curve Sorted= 0
DSS Export Volume Flow Curves= 0
DXF OffsetX= 0
DXF OffsetY= 0
DXF ScaleX= 1
DXF ScaleY= 10

--- Cypress Creek.p01 (plan) ---

Plan Title=Multiple Run
Short Identifier=Multiple
Geom File=g01
Flow File=f01
Subcritical Flow
K Sum by GR= 0
Std Step Tol= 0.01
Critical Tol= 0.01
Num of Std Step Trials= 20
Max Error Tol= 0.3
Flow Tol Ratio= 0.001
Split Flow NTrial= 30
Split Flow Tol= 0.02
Split Flow Ratio= 0.02
Log Output Level= 0
Friction Slope Method= 1
Unsteady Friction Slope Method= 2
Unsteady Bridges Friction Slope Method= 1
Parabolic Critical Depth
Global Vel Dist=  1 , 1 , 1
Global Log Level= 0
CheckData=True
Encroach Param= -1, 0, 0, 0
BEGIN DESCRIPTION:
Multiple Run
END DESCRIPTION:

--- Cypress Creek.f01 (steady flow) ---

Flow Title=Multiple
Number of Profiles=7
Profile Names=10-year,25-year,50-year,1pct_min,100-year,1pct_plu,500-year
River Rch & RM= Cypress Creek,Reach-1,100161
     360     569     754     487     971    1937    1579
River Rch & RM= Cypress Creek,Reach-1,99712
     664    1097    1497     991    1978    3947    3401
River Rch & RM= Cypress Creek,Reach-1,96911
    1945    3416    4855    3330    6644   13256   12295
River Rch & RM= Cypress Creek,Reach-1,89178
    3450    6224    9007    6276   12522   24985   23932
River Rch & RM= Cypress Creek,Reach-1,83817
    3665    6588    9510    6608   13185   26307   25052
River Rch & RM= Cypress Creek,Reach-1,79689
    3761    6764    9767    6789   13546   27027   25750
River Rch & RM= Cypress Creek,Reach-1,78345
    4663    8464   12300    8598   17154   34227   32982
River Rch & RM= Cypress Creek,Reach-1,74639
    4805    8723   12675    8858   17673   35263   33964
River Rch & RM= Cypress Creek,Reach-1,70580
    6034   11037   16120   11313   22572   45037   43752
River Rch & RM= Cypress Creek,Reach-1,62897
    6217   11379   16627   11673   23290   46470   45178
River Rch & RM= Cypress Creek,Reach-1,60530
    5288    9647   14082    9911   19775   39455   38730
River Rch & RM= Cypress Creek,Reach-1,55047
    7824   14464   21307   15121   30170   60197   60064
River Rch & RM= Cypress Creek,Reach-1,52987
    7853   14514   21378   15168   30265   60387   60232
River Rch & RM= Cypress Creek,Reach-1,52225
    8049   14877   21915   15549   31025   61903   61744
River Rch & RM= Cypress Creek,Reach-1,49992
    8002   14762   21715   15385   30697   61248   60909
River Rch & RM= Cypress Creek,Reach-1,44810
    8053   14855   21852   15481   30888   61630   61281
River Rch & RM= Cypress Creek,Reach-1,44241
    8070   14873   21864   15478   30883   61619   61181
River Rch & RM= Cypress Creek,Reach-1,40881
    9668   17871   26325   18667   37247   74317   74018
River Rch & RM= Cypress Creek,Reach-1,32164
   12126   22551   33346   23698   47284   94345   94217
River Rch & RM= Cypress Creek,Reach-1,30874
   12570   23321   34436   24439   48761   97292   96845
River Rch & RM= Cypress Creek,Reach-1,28824
   14119   26277   38888   27655   55179  110096  110025
River Rch & RM= Cypress Creek,Reach-1,28117
   13990   25989   38411   27278   54427  108596  108226
River Rch & RM= Cypress Creek,Reach-1,21974
   14692   27291   40336   28642   57148  114026  113602
River Rch & RM= Cypress Creek,Reach-1,16168
   17143   31928   47280   33629   67098  133879  133798
River Rch & RM= Cypress Creek,Reach-1,10514
   17139   31906   47232   33583   67007  133696  133522
River Rch & RM= Cypress Creek,Reach-1,8444
   17073   31758   46988   33391   66624  132933  132612
River Rch & RM= Cypress Creek,Reach-1,5599
   17204   32004   47353   33651   67143  133968  133646
River Rch & RM= Cypress Creek,Reach-1,4875
   17179   31942   47249   33566   66974  133630  133226
River Rch & RM= Cypress Creek,Reach-1,2094
   17034   31638   46763   33195   66233  132151  131542
Boundary for River Rch & Prof#=Cypress Creek,Reach-1,1
Up Type=0
Dn Type=3
Dn Slope=0.005
Boundary for River Rch & Prof#=Cypress Creek,Reach-1,2
Up Type=0
Dn Type=3
Dn Slope=0.005
Boundary for River Rch & Prof#=Cypress Creek,Reach-1,3
Up Type=0
Dn Type=3
Dn Slope=0.005
Boundary for River Rch & Prof#=Cypress Creek,Reach-1,4
Up Type=0
Dn Type=3
Dn Slope=0.005
Boundary for River Rch & Prof#=Cypress Creek,Reach-1,5
Up Type=0
Dn Type=3
Dn Slope=0.005
Boundary for River Rch & Prof#=Cypress Creek,Reach-1,6
Up Type=0
Dn Type=3
Dn Slope=0.005
Boundary for River Rch & Prof#=Cypress Creek,Reach-1,7
Up Type=0
Dn Type=3
Dn Slope=0.005

--- Cypress Creek.g01 (geometry) ---

Geom Title=Existing Conditions
Program Version=4.10

River Reach=Cypress Creek   ,Reach-1
Reach XY= 30
        1952225.       13949525.      1954078.55     13942326.47
      1955867.06     13941381.14      1956544.79     13938654.91
      1958169.54     13938077.45      1957777.22     13935180.92
      1960144.27     13931804.98       1961154.9     13931074.91
      1963630.86     13932522.93       1964941.7     13932158.63
      1964678.74     13930026.56      1967554.58     13925844.77
      1976666.86     13920431.06      1975724.61     13919454.87
      1976501.67     13915197.31      1980041.79     13914758.56
      1982171.88     13911723.37      1981830.52     13910222.57
        1983775.       13908475.      1986177.42     13908019.46
      1986935.43     13906626.05      1988877.31     13907369.18
      1989633.28     13904878.06      1992142.06     13905008.52
      1993722.74     13902569.06      1993230.83      13900472.7
      1995768.94     13897933.14      1997190.18     13897274.57
       1998635.5      13898323.8        2000775.       13898025.

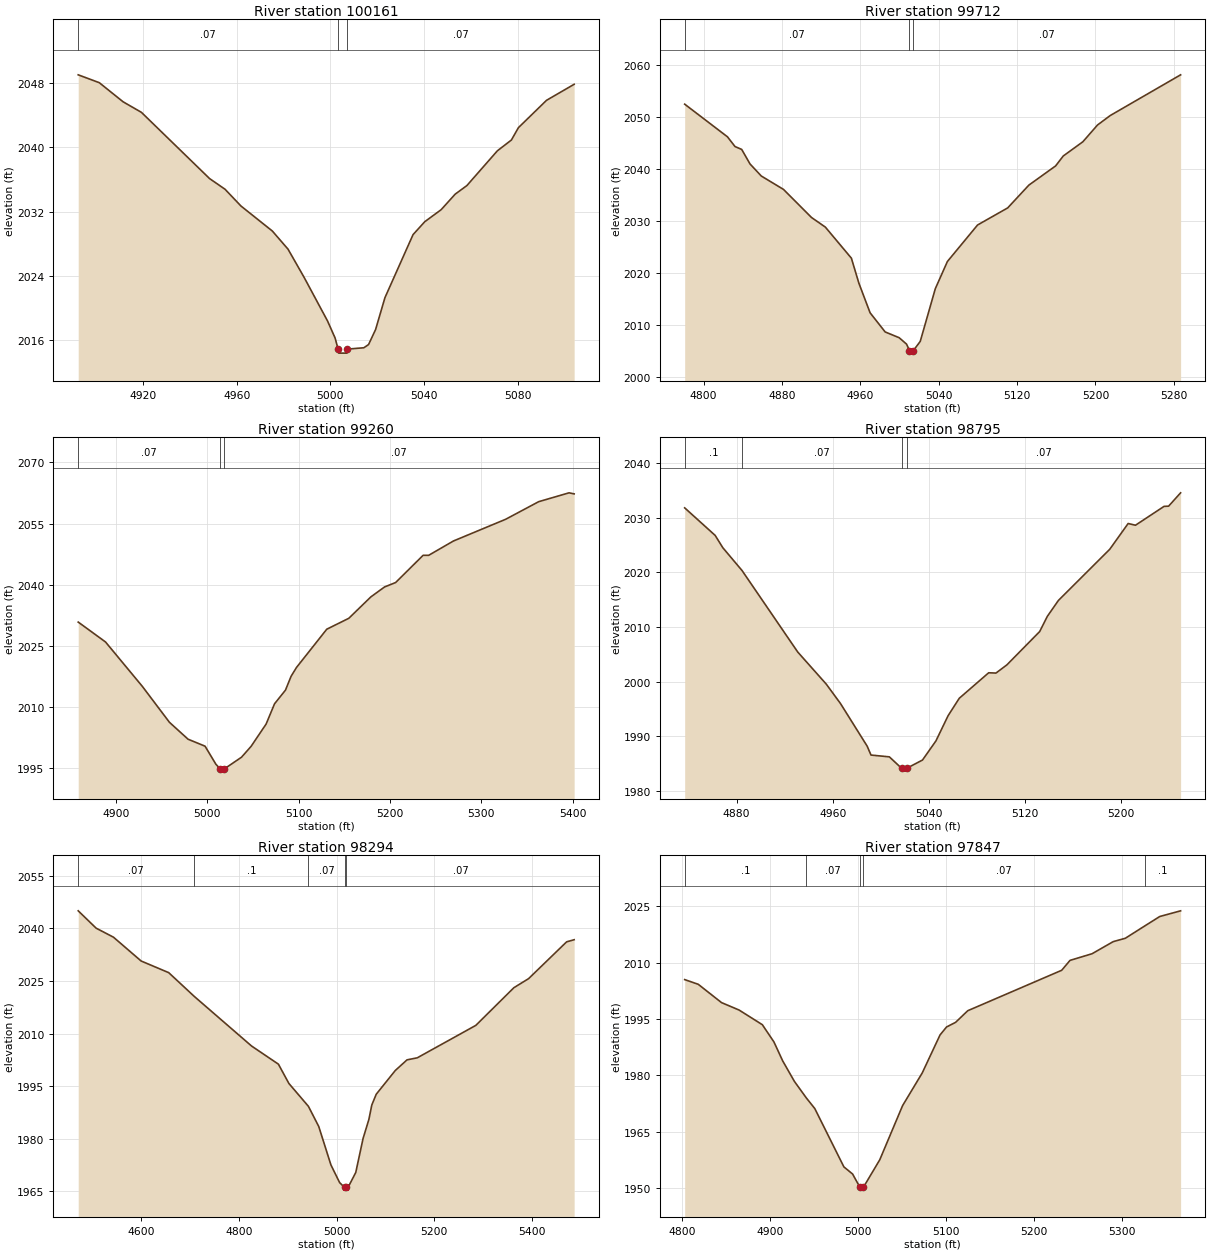
Type RM Length L Ch R = 1 ,100161  ,449,449,449
BEGIN DESCRIPTION:
Cypress Creek 160.0
END DESCRIPTION:
XS GIS Cut Line= 3
      1952425.02     13949325.01        1952325.       13949275.
      1952225.03       13949275.
#Sta/Elev= 30
  4892.3 2049.05  4901.3 2048.07  4911.5 2045.68  4919.3 2044.37  4948.4 2036.11
    4955 2034.78  4961.8 2032.69  4975.2 2029.57  4981.9 2027.31  4988.7 2023.83
  4998.8 2018.34    5002 2016.23  5003.3 2014.84  5003.6 2014.34  5007.1 2014.34
  5007.3 2014.84  5014.3 2015.01  5016.3 2015.41  5019.3 2017.28  5023.3 2021.26
  5035.3 2029.12  5040.3 2030.73  5047.3 2032.23  5053.3 2034.17  5058.3 2035.24
  5071.3 2039.57  5077.3 2040.92  5080.3 2042.46  5092.3 2045.87  5104.1 2047.87
#Mann= 3 ,-1 , 0
  4892.3     .07       0  5003.3     .05       0  5007.3     .07       0
Bank Sta=5003.3,5007.3
XS Rating Curve= 0 ,0
Exp/Cntr=0.3,0.1

Type RM Length L Ch R = 1 ,99712   ,452,452,452
BEGIN DESCRIPTION:
Cypress Creek 159.0
END DESCRIPTION:
XS GIS Cut Line= 3
        1952643.     13949008.61        1952475.       13948875.
      1952190.88     13948809.16
#Sta/Elev= 30
  4780.7 2052.41  4824.4 2046.13  4832.1 2044.26  4838.9 2043.71  4847.4 2040.92
  4858.9  2038.6  4881.6 2036.02  4910.2 2030.62  4924.3 2028.78  4950.9  2022.8
  4958.5 2018.02    4970  2012.3  4985.4 2008.62  4999.7 2007.51  5007.2 2006.28
  5010.2 2005.05  5010.4 2004.55  5014.2 2005.05  5021.2 2006.81  5036.6 2016.95
  5048.9 2022.16  5079.7 2029.18  5110.5 2032.47  5132.1 2036.85  5159.4 2040.54
  5167.2 2042.45  5187.2 2045.18  5202.2 2048.41  5215.2 2050.23    5287 2058.05
#Mann= 3 ,-1 , 0
  4780.7     .07       0  5010.2     .05       0  5014.2     .07       0
Bank Sta=5010.2,5014.2
XS Rating Curve= 0 ,0
Exp/Cntr=0.3,0.1

Type RM Length L Ch R = 1 ,99260   ,465,465,465
BEGIN DESCRIPTION:
Cypress Creek 158.0
END DESCRIPTION:
XS GIS Cut Line= 3
      1952725.02     13948575.02        1952625.       13948475.
      1952225.19     13948436.52
#Sta/Elev= 30
  4858.6 2030.82  4888.5 2025.94  4928.8 2015.05  4958.5 2006.23  4978.9 2002.08
  4997.5 2000.37  5009.4 1995.93  5014.3 1994.75  5014.6 1994.25  5018.1 1994.25
  5018.3 1994.75  5037.4 1997.66  5047.9 2000.32  5064.4 2005.81  5073.6 2010.77
  5085.6 2014.13  5091.7 2017.51  5097.7  2019.7  5130.8 2029.07  5154.9 2031.74
  5179.1    2037  5194.1 2039.44  5206.2 2040.52  5236.3  2047.2  5242.4  2047.2
  5269.5 2050.71  5326.7 2056.04  5362.9 2060.36  5396.1 2062.53  5401.7 2062.27
#Mann= 3 ,-1 , 0
  4858.6     .07       0  5014.3     .05       0  5018.3     .07       0
Bank Sta=5014.3,5018.3
XS Rating Curve= 0 ,0
Exp/Cntr=0.3,0.1

Type RM Length L Ch R = 1 ,98795   ,501,501,501
BEGIN DESCRIPTION:
Cypress Creek 157.0
END DESCRIPTION:
XS GIS Cut Line= 3
        1952825.       13948075.        1952675.       13948025.
      1952424.97     13948075.01
#Sta/Elev= 30
  4836.7  2031.8  4862.1 2026.76  4868.5  2024.5  4884.5 2020.33  4930.9 2005.42
  4954.7 1999.54  4966.5    1996  4988.7 1988.21  4991.9 1986.58  5007.2 1986.25
  5017.5 1984.14  5017.7 1983.64  5021.2 1983.64  5021.5 1984.14  5034.8 1985.67
    5046 1989.17  5056.1 1993.77  5065.4 1996.96  5089.9 2001.63    5096 2001.58
  5105.1 2003.08  5132.4 2009.17  5138.8 2011.96    5148 2014.86  5190.8 2024.23
  5206.1 2028.94  5212.2 2028.62    5236 2032.07  5239.8 2032.11  5249.8 2034.55
#Mann= 4 ,-1 , 0
  4836.7      .1       0  4884.5     .07       0  5017.5     .05       0
  5021.5     .07       0
Bank Sta=5017.5,5021.5
XS Rating Curve= 0 ,0
Exp/Cntr=0.3,0.1

Type RM Length L Ch R = 1 ,98294   ,447,447,447
BEGIN DESCRIPTION:
Cypress Creek 156.0
END DESCRIPTION:
XS GIS Cut Line= 4
      1953049.59     13947840.11      1952877.34     13947566.91
        1952675.       13947525.      1952188.41       13947539.
#Sta/Elev= 30
  4470.3 2045.02  4507.1 2040.07  4542.6  2037.5  4599.3 2030.71  4655.8 2027.39
  4708.3  2020.6  4825.5 2006.48  4880.6  2001.3  4902.1 1995.79  4942.1 1989.28
  4963.3 1983.52  4988.2 1972.58  5006.1 1967.52  5016.1 1966.17  5016.4 1965.67
  5020.1 1966.17  5024.1 1966.37  5039.1 1970.41  5054.1  1980.1  5066.1 1985.59
    5072 1989.65  5081.1 1992.73  5120.1 1999.49  5144.2 2002.53  5165.2 2003.11
  5285.2 2012.36  5363.2  2023.1  5393.3 2025.68  5471.3 2036.18  5486.7 2036.78
#Mann= 5 ,-1 , 0
  4470.3     .07       0  4708.3      .1       0  4942.1     .07       0
  5016.1     .05       0  5020.1     .07       0
Bank Sta=5016.1,5020.1
XS Rating Curve= 0 ,0
Exp/Cntr=0.3,0.1

Type RM Length L Ch R = 1 ,97847   ,483,483,483
BEGIN DESCRIPTION:
Cypress Creek 155.0
END DESCRIPTION:
XS GIS Cut Line= 3
      1952799.79     13947043.43        1952625.       13947125.
      1952302.17     13947307.63
#Sta/Elev= 30
  4802.5 2005.48  4817.9 2004.23  4844.4 1999.35  4864.3 1997.38  4890.8 1993.47
    4904 1988.87  4913.9 1983.85  4927.2 1978.39  4940.9 1973.94  4950.4 1971.15
  4983.5 1955.61  4993.4 1953.71  5001.7 1950.19  5001.9 1949.69  5005.7 1950.19
  5024.3 1957.51  5050.2 1971.91  5072.6 1980.64  5092.8 1990.74  5100.2 1992.86
  5110.5  1994.1  5124.3 1997.19  5231.1 2007.96  5240.6  2010.6  5265.6 2012.36
  5289.7 2015.59  5303.5 2016.49  5325.5 2019.76  5342.6 2022.28  5366.3 2023.79
#Mann= 5 ,-1 , 0
  4802.5      .1       0  4940.9     .07       0  5001.7     .05       0
  5005.7     .07       0  5325.5      .1       0
Bank Sta=5001.7,5005.7
XS Rating Curve= 0 ,0
Exp/Cntr=0.3,0.1

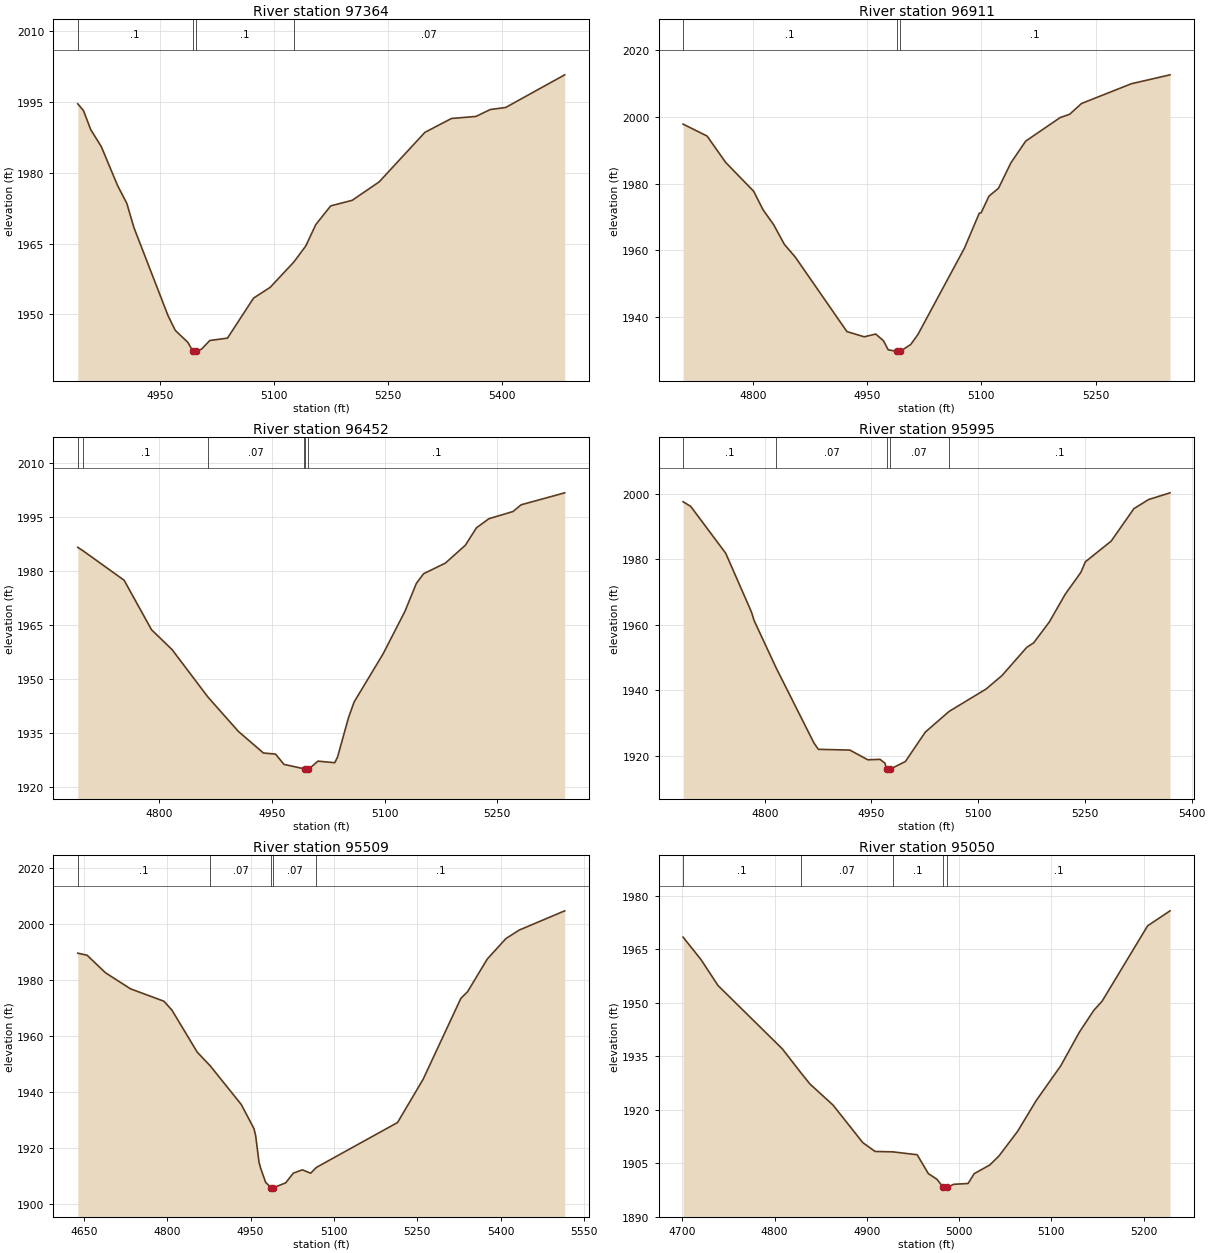
Type RM Length L Ch R = 1 ,97364   ,453,453,453
BEGIN DESCRIPTION:
Cypress Creek 154.0
END DESCRIPTION:
XS GIS Cut Line= 4
      1952774.96     13946724.99        1952625.       13946675.
      1952487.11     13946714.62      1952308.05     13947001.94
#Sta/Elev= 30
    4842 1994.62  4849.5  1993.2    4859 1989.17    4873 1985.53  4894.3 1977.31
  4906.5  1973.5  4915.9 1968.35  4960.7  1949.7  4970.2 1946.58  4986.8 1944.03
    4993 1942.26  4993.3 1941.76    4997 1942.26  5004.4 1942.56  5015.6 1944.44
  5038.8 1944.94  5073.1 1953.43    5095 1955.72    5126 1961.07  5141.8  1964.5
  5154.9 1969.02  5174.5 1972.98  5202.7 1974.16  5238.2 1978.07  5298.3 1988.57
  5333.2 1991.51  5365.5 1991.95  5384.2 1993.41  5404.4 1993.84  5482.1 2000.77
#Mann= 4 ,-1 , 0
    4842      .1       0    4993     .05       0    4997      .1       0
    5126     .07       0
Bank Sta=4993,4997
XS Rating Curve= 0 ,0
Exp/Cntr=0.3,0.1

Type RM Length L Ch R = 1 ,96911   ,459,459,459
BEGIN DESCRIPTION:
Cypress Creek 153.0
END DESCRIPTION:
XS GIS Cut Line= 3
      1952925.01     13946525.02        1952775.       13946275.
      1952439.85      13946181.2
#Sta/Elev= 30
  4708.2 1997.83  4739.7 1994.25  4764.2 1986.34  4800.9 1977.71  4813.2 1972.17
  4827.2 1967.68  4841.2 1961.81  4855.6 1957.97  4923.4 1935.66  4946.1 1934.09
  4961.3 1934.92  4971.5 1932.88  4977.6 1930.21  4989.2  1929.7  4989.4  1929.2
  4993.2  1929.7  5007.2 1931.79  5016.6 1934.76  5077.8 1960.68  5097.3 1971.17
  5099.7 1971.26    5110 1976.25  5122.5 1978.61  5138.7 1986.19  5158.2 1992.73
  5203.5 1999.79    5216 2000.79  5231.5    2004  5296.9 2009.92  5347.8  2012.6
#Mann= 3 ,-1 , 0
  4708.2      .1       0  4989.2     .05       0  4993.2      .1       0
Bank Sta=4989.2,4993.2
XS Rating Curve= 0 ,0
Exp/Cntr=0.3,0.1

Type RM Length L Ch R = 1 ,96452   ,457,457,457
BEGIN DESCRIPTION:
Cypress Creek 152.0
END DESCRIPTION:
XS GIS Cut Line= 3
        1953175.     13946324.98        1953125.       13946025.
      1952923.08     13945745.66
#Sta/Elev= 30
  4691.2 1986.52  4697.8 1985.63    4753 1977.36  4789.5  1963.6  4816.9 1958.07
  4864.7 1944.87  4905.1 1935.35  4938.6 1929.32  4954.7 1929.02  4965.9 1926.16
  4992.8 1924.93  4994.6 1924.78  4994.8 1924.28  4998.6 1924.78  5011.2 1927.06
  5033.6 1926.62  5037.3 1928.17  5052.1 1939.27  5059.5 1943.54  5098.1 1956.92
  5127.2 1968.76  5142.3 1976.47    5152 1979.18    5181 1982.14  5207.6  1987.1
  5222.4 1991.95    5239 1994.48  5271.2 1996.49  5281.9 1998.35    5340 2001.68
#Mann= 6 ,-1 , 0
  4691.2     .07       0  4697.8      .1       0  4864.7     .07       0
  4992.8      .1       0  4994.6     .05       0  4998.6      .1       0
Bank Sta=4994.6,4998.6
XS Rating Curve= 0 ,0
Exp/Cntr=0.3,0.1

Type RM Length L Ch R = 1 ,95995   ,486,486,486
BEGIN DESCRIPTION:
Cypress Creek 151.0
END DESCRIPTION:
XS GIS Cut Line= 3
      1953575.01     13945925.01        1953375.       13945675.
      1953030.21     13945557.62
#Sta/Elev= 30
  4685.2 1997.52    4696 1996.07  4745.1 1981.78  4781.3 1963.83  4785.1 1961.18
  4816.3 1946.63  4868.9 1923.92  4875.3 1921.89  4919.6 1921.66  4944.8 1918.69
  4961.9 1918.83  4968.9 1917.67  4971.4 1915.73  4971.6 1915.23  4975.4 1915.73
  4997.7 1918.18  5025.6 1927.14    5059 1933.45  5111.2 1940.33  5133.4 1944.42
  5168.3 1953.06  5177.8 1954.38  5199.9 1960.77  5222.1 1969.19  5244.3 1975.95
  5250.6 1979.16  5286.9 1985.49  5318.8  1995.4  5339.4 1998.17  5369.6 2000.23
#Mann= 5 ,-1 , 0
  4685.2      .1       0  4816.3     .07       0  4971.4     .05       0
  4975.4     .07       0    5059      .1       0
Bank Sta=4971.4,4975.4
XS Rating Curve= 0 ,0
Exp/Cntr=0.3,0.1

Type RM Length L Ch R = 1 ,95509   ,459,459,459
BEGIN DESCRIPTION:
Cypress Creek 150.0
END DESCRIPTION:
XS GIS Cut Line= 3
      1953831.68     13945214.68        1953475.       13945225.
      1952956.05     13945203.97
#Sta/Elev= 30
    4639 1989.59  4655.9 1988.84  4688.9 1982.59    4734 1976.85    4794 1972.44
  4808.5 1969.24    4854 1954.24  4877.4 1949.35  4933.2 1935.56  4956.1 1926.93
  4959.1 1924.43  4965.1 1915.01  4968.1  1912.8  4977.1 1907.75  4987.1 1905.84
  4987.3 1905.34  4991.1 1905.84  5013.1 1907.58  5026.8 1911.03  5043.1 1912.23
  5058.1 1911.02  5068.4  1913.1  5214.4 1929.12  5260.5 1944.59  5328.3 1973.44
  5340.4 1975.83  5375.9  1987.5  5409.4  1994.8  5433.4 1997.84  5515.2 2004.71
#Mann= 5 ,-1 , 0
    4639      .1       0  4877.4     .07       0  4987.1     .05       0
  4991.1     .07       0  5068.4      .1       0
Bank Sta=4987.1,4991.1
XS Rating Curve= 0 ,0
Exp/Cntr=0.3,0.1

Type RM Length L Ch R = 1 ,95050   ,433,433,433
BEGIN DESCRIPTION:
Cypress Creek 149.0
END DESCRIPTION:
XS GIS Cut Line= 3
      1953675.02       13944875.        1953375.       13944825.
      1953174.97     13944724.99
#Sta/Elev= 30
  4700.9  1968.4  4720.4 1962.08  4738.7 1954.86  4808.6 1937.06  4828.8 1930.33
  4838.4 1927.25  4863.4 1921.35  4895.7 1910.82    4909 1908.35  4928.3 1908.23
  4954.6 1907.43  4966.8 1902.12  4975.9 1900.59    4983 1898.29  4983.3 1897.79
  4986.8 1897.79    4987 1898.29  4994.2 1899.14  5009.8 1899.37  5016.5 1902.14
  5033.3 1904.55  5043.4 1907.11  5063.5 1913.99  5083.6 1922.59  5110.3 1932.36
  5130.4 1941.76  5146.1 1947.89    5155 1950.42  5204.4 1971.57  5228.7 1975.77
#Mann= 5 ,-1 , 0
  4700.9      .1       0  4828.8     .07       0  4928.3      .1       0
    4983     .05       0    4987      .1       0
Bank Sta=4983,4987
XS Rating Curve= 0 ,0
Exp/Cntr=0.3,0.1

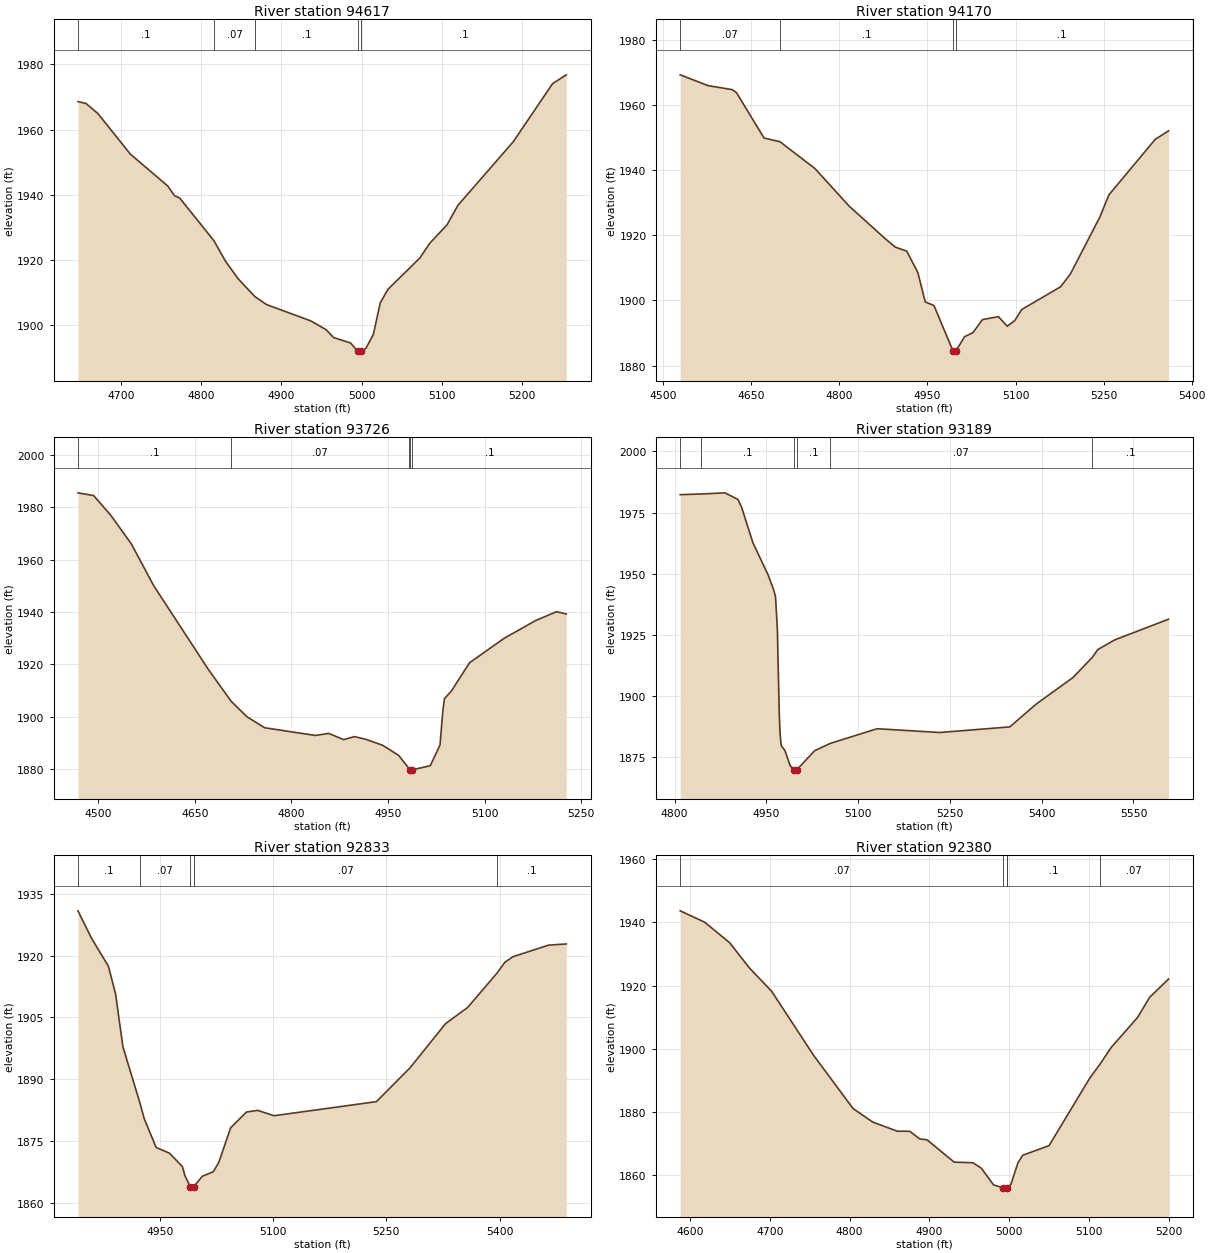
Type RM Length L Ch R = 1 ,94617   ,447,447,447
BEGIN DESCRIPTION:
Cypress Creek 148.0
END DESCRIPTION:
XS GIS Cut Line= 3
        1953725.       13944675.        1953475.       13944425.
        1953225.       13944375.
#Sta/Elev= 30
  4646.4 1968.59  4656.4 1968.01  4671.3 1964.91  4711.6  1952.5  4758.3  1942.7
  4766.7 1939.73  4773.1 1939.03  4815.9  1925.9  4830.4 1919.57  4846.2  1914.2
  4866.8  1908.8  4881.3 1906.35  4936.5 1901.34  4955.5 1898.66  4964.9 1896.24
  4986.2 1894.55  4995.1 1891.95  4995.3 1891.45  4999.1 1891.95  5005.2  1892.9
  5014.5 1897.19  5023.1 1906.87  5032.8 1911.05  5072.6 1920.67  5084.8 1925.15
  5106.3 1930.79  5119.9 1936.79  5188.9 1956.29  5237.8 1974.08  5254.9 1976.79
#Mann= 5 ,-1 , 0
  4646.4      .1       0  4815.9     .07       0  4866.8      .1       0
  4995.1     .05       0  4999.1      .1       0
Bank Sta=4995.1,4999.1
XS Rating Curve= 0 ,0
Exp/Cntr=0.3,0.1

Type RM Length L Ch R = 1 ,94170   ,444,444,444
BEGIN DESCRIPTION:
Cypress Creek 147.0
END DESCRIPTION:
XS GIS Cut Line= 4
      1954089.28      13944368.4      1953832.82     13944196.08
        1953725.       13944075.      1953524.98     13943774.97
#Sta/Elev= 30
  4528.9  1969.2  4576.4 1965.88  4617.4 1964.66  4624.7 1963.75  4671.7 1949.81
  4698.8 1948.68  4758.5 1940.43  4816.4 1928.96  4878.3 1918.89  4895.3 1916.33
  4914.7 1915.11  4933.6 1908.56  4946.3 1899.52  4961.2 1898.39  4993.9 1884.31
  4994.1 1883.81  4997.9 1884.31  5013.2 1888.85  5027.5  1890.1  5043.7 1894.09
  5070.8 1895.01    5086 1892.07  5098.9 1893.84  5110.5 1897.18  5176.8 1904.17
  5193.4 1908.08  5243.8 1925.63    5259 1932.35  5337.7 1949.36  5360.6 1952.01
#Mann= 4 ,-1 , 0
  4528.9     .07       0  4698.8      .1       0  4993.9     .05       0
  4997.9      .1       0
Bank Sta=4993.9,4997.9
XS Rating Curve= 0 ,0
Exp/Cntr=0.3,0.1

Type RM Length L Ch R = 1 ,93726   ,537,537,537
BEGIN DESCRIPTION:
Cypress Creek 146.0
END DESCRIPTION:
XS GIS Cut Line= 3
      1954375.02     13944075.02        1953975.       13943725.
      1953785.27     13943599.71
#Sta/Elev= 30
  4468.2 1985.48  4492.5 1984.44  4519.1 1976.94  4550.9 1966.09    4586 1949.99
    4671 1917.98  4706.4 1905.86  4730.6 1900.02  4758.2 1895.78  4836.9 1892.84
  4857.9 1893.61  4881.2 1891.24  4897.8 1892.39  4915.5 1891.37  4941.6 1889.09
  4966.6 1885.22  4982.7  1880.2  4983.7 1879.71    4984 1879.21  4987.7 1879.71
  5015.8 1881.29  5030.9 1889.23  5035.2 1902.04  5037.8 1906.91  5048.6 1909.81
  5076.7 1920.58  5130.3 1929.89  5179.3 1936.69    5212  1940.1  5227.1 1939.21
#Mann= 5 ,-1 , 0
  4468.2      .1       0  4706.4     .07       0  4982.7      .1       0
  4983.7     .05       0  4987.7      .1       0
Bank Sta=4983.7,4987.7
XS Rating Curve= 0 ,0
Exp/Cntr=0.3,0.1

Type RM Length L Ch R = 1 ,93189   ,356,356,356
BEGIN DESCRIPTION:
Cypress Creek 145.0
END DESCRIPTION:
XS GIS Cut Line= 4
      1954611.72     13943462.76      1954425.12     13943504.94
      1954108.73     13943486.36      1953824.47     13943543.52
#Sta/Elev= 30
  4809.1 1982.33    4843 1982.58  4882.1 1983.07  4903.4 1980.38  4909.4 1977.21
    4928 1962.59  4952.6 1949.59  4961.8 1943.41  4964.9 1940.57    4968 1926.96
    4969  1914.7  4971.1 1892.17  4972.4 1884.33  4974.1 1879.68  4980.3 1877.55
  4988.8 1871.39  4995.5 1869.65  4995.7 1869.15  4999.5 1869.65  5028.8 1877.49
  5054.5 1880.51    5131 1886.51  5233.4 1884.96  5347.9 1887.26  5390.8 1896.56
  5451.2 1907.48  5482.6 1915.69  5491.7 1918.91  5519.3 1922.86  5607.3 1931.34
#Mann= 6 ,-1 , 0
  4809.1     .07       0    4843      .1       0  4995.5     .05       0
  4999.5      .1       0  5054.5     .07       0  5482.6      .1       0
Bank Sta=4995.5,4999.5
XS Rating Curve= 0 ,0
Exp/Cntr=0.3,0.1

Type RM Length L Ch R = 1 ,92833   ,453,453,453
BEGIN DESCRIPTION:
Cypress Creek 144.0
END DESCRIPTION:
XS GIS Cut Line= 3
      1954374.96     13943175.01        1954225.       13943225.
       1953824.7      13943504.5
#Sta/Elev= 30
  4841.9 1930.85    4860 1924.14  4882.2 1917.39  4891.7 1910.66  4901.4 1897.84
  4923.8 1884.26  4929.6 1880.37  4945.4 1873.38  4963.1 1871.98  4980.2 1868.72
  4983.4 1866.56  4990.8 1863.76  4991.1 1863.26  4994.9 1863.76  5006.4 1866.38
    5021 1867.48  5028.3 1869.76    5044 1878.16  5064.9 1881.98  5079.6 1882.39
  5101.5 1881.09  5236.9 1884.51  5281.3  1892.7  5328.4 1903.45  5357.6 1907.37
  5396.6 1915.75  5407.1 1918.38  5417.5  1919.7  5464.7 1922.52  5488.2  1922.8
#Mann= 5 ,-1 , 0
  4841.9      .1       0  4923.8     .07       0  4990.8     .05       0
  4994.9     .07       0  5396.6      .1       0
Bank Sta=4990.8,4994.9
XS Rating Curve= 0 ,0
Exp/Cntr=0.3,0.1

Type RM Length L Ch R = 1 ,92380   ,296,296,296
BEGIN DESCRIPTION:
Cypress Creek 143.0
END DESCRIPTION:
XS GIS Cut Line= 3
      1954474.99       13942925.        1954075.       13942825.
        1953875.       13942825.
#Sta/Elev= 30
  4587.6 1943.67  4618.3 1940.07  4649.7 1933.56  4674.4 1925.58  4702.3  1918.2
  4754.8 1897.97  4804.3 1881.11  4829.1  1876.8    4860 1873.92  4875.4  1873.9
  4887.9 1871.49  4897.1  1871.2  4931.1 1864.13  4954.7 1863.94  4965.1 1862.23
  4980.6 1856.91  4991.8 1856.09  4992.2 1855.59  4996.8 1856.09  4997.1 1856.11
  5002.1 1856.98  5011.1 1863.93  5017.1 1866.31  5050.1 1869.36  5101.1 1890.71
  5113.7 1895.03  5128.1 1900.46  5161.1 1909.93  5176.1 1916.26  5199.9 1922.08
#Mann= 5 ,-1 , 0
  4587.6     .07       0  4991.8     .05       0  4996.8     .07       0
  4997.1      .1       0  5113.7     .07       0
Bank Sta=4991.8,4996.8
XS Rating Curve= 0 ,0
Exp/Cntr=0.3,0.1

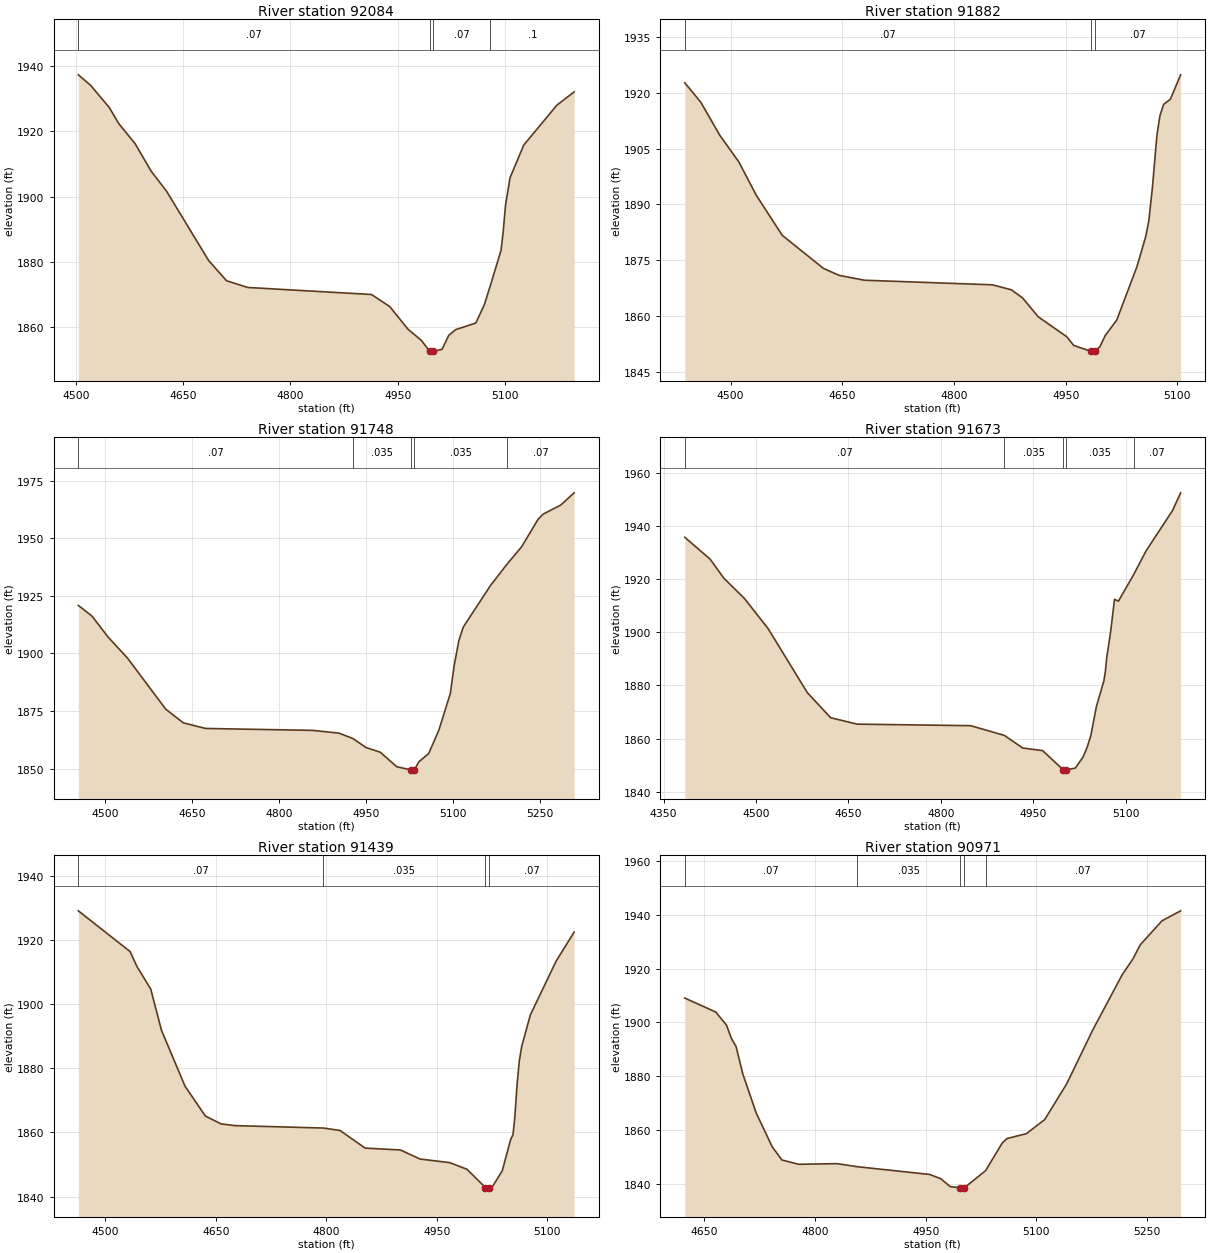
Type RM Length L Ch R = 1 ,92084   ,202,202,202
BEGIN DESCRIPTION:
Mapping XS 868f5d40
END DESCRIPTION:
XS GIS Cut Line= 3
      1954469.93     13942821.71       1954155.6     13942556.61
      1953889.03     13942465.18
#Sta/Elev= 30
  4503.6 1937.28  4520.8 1934.07  4546.8 1927.28  4560.1 1922.34    4583 1916.18
  4605.4 1907.77  4626.8 1901.67  4685.7 1880.41  4710.7 1874.21  4740.5 1872.14
  4913.3 1869.99  4938.9 1866.29  4964.3 1859.37  4983.3 1855.88  4994.8 1852.53
  4995.2 1852.03  4999.8 1852.53  5011.9 1853.18  5021.3 1857.47  5030.8 1859.21
  5059.2 1861.27    5071 1866.82  5079.6 1872.82  5094.4  1883.5  5097.5 1889.39
  5100.7 1897.41    5107 1905.77  5126.1 1915.75  5172.5    1928  5196.6 1932.05
#Mann= 4 ,-1 , 0
  4503.6     .07       0  4994.8     .05       0  4999.8     .07       0
  5079.6      .1       0
Bank Sta=4994.8,4999.8
XS Rating Curve= 0 ,0
Exp/Cntr=0.3,0.1

Type RM Length L Ch R = 1 ,91882   ,134,134,134
BEGIN DESCRIPTION:
Cypress Creek 142.0
END DESCRIPTION:
XS GIS Cut Line= 3
      1954474.99     13942724.99        1954075.       13942325.
      1953974.97       13942325.
#Sta/Elev= 30
  4438.6 1922.71  4460.2 1917.44  4485.6 1908.59  4511.1 1901.45  4534.7 1892.43
  4569.5 1881.69  4624.7 1872.82  4645.9 1870.93  4679.9 1869.63  4851.7  1868.4
  4877.1 1867.06    4892  1864.9  4913.2  1859.8  4951.4 1854.45  4960.8 1852.11
  4983.7 1850.54  4984.1 1850.04  4988.7 1850.54  4995.9 1851.75  5003.2 1854.81
  5018.5 1858.91  5045.5 1873.19  5057.5 1881.41  5061.5 1885.43  5066.5 1894.68
  5072.5 1908.63  5076.5 1913.85  5081.5  1916.9  5090.5 1918.27  5104.3 1924.84
#Mann= 3 ,-1 , 0
  4438.6     .07       0  4983.7     .05       0  4988.7     .07       0
Bank Sta=4983.7,4988.7
XS Rating Curve= 0 ,0
Exp/Cntr=0.3,0.1

Type RM Length L Ch R = 1 ,91748   ,75,75,75
BEGIN DESCRIPTION:
Cypress Creek 141.1
END DESCRIPTION:
XS GIS Cut Line= 4
      1954528.98     13942635.84      1954213.91     13942255.67
      1954068.07     13942172.34      1953896.17     13942083.78
#Sta/Elev= 30
  4453.2 1920.87  4476.7 1916.25  4504.3 1907.19  4538.2 1897.92    4604 1875.77
  4634.3 1869.85  4672.7 1867.41  4857.9 1866.57  4902.8 1865.36  4926.2  1863.1
  4949.7 1859.09  4973.9  1857.1  5002.4 1850.77  5027.6 1849.37  5027.9 1848.87
  5032.6 1849.37  5040.4 1852.88  5057.5 1856.54    5075 1866.69  5094.8 1882.67
  5101.4  1894.8  5109.5 1905.58  5116.9 1911.38  5163.6 1929.36  5192.2 1938.68
  5217.7 1946.35    5246 1958.25  5254.8 1960.52  5285.1 1964.46  5308.3 1969.78
#Mann= 5 ,-1 , 0
  4453.2     .07       0  4926.2    .035       0  5027.6    .035       0
  5032.6    .035       0  5192.2     .07       0
Bank Sta=5027.6,5032.6
XS Rating Curve= 0 ,0
Exp/Cntr=0.3,0.1

Type RM Length L Ch R = 1 ,91673   ,234,234,234
BEGIN DESCRIPTION:
Mapping XS 771f168c
END DESCRIPTION:
XS GIS Cut Line= 2
      1954623.58     13942597.01      1954057.59     13942025.56
#Sta/Elev= 30
  4384.5 1935.83  4425.5 1927.63  4447.8 1920.44  4481.2 1912.79  4519.6 1901.44
  4583.2 1877.31  4621.2 1867.83  4664.2 1865.42  4848.2 1864.84  4902.8 1861.18
  4932.8 1856.41  4964.9 1855.45  4998.4 1848.21  4998.8 1847.71  5003.5 1848.21
  5017.9 1848.83  5030.5 1853.03    5037 1856.57  5043.1 1861.05  5052.2 1872.08
  5064.3 1881.72  5066.7 1885.13  5068.8 1890.28  5075.2 1900.12  5081.6 1912.49
  5087.9 1911.76  5112.8 1921.86  5132.5 1930.62  5175.8 1945.98  5188.8  1952.6
#Mann= 5 ,-1 , 0
  4384.5     .07       0  4902.8    .035       0  4998.4    .035       0
  5003.5    .035       0  5112.8     .07       0
Bank Sta=4998.4,5003.5
XS Rating Curve= 0 ,0
Exp/Cntr=0.3,0.1

Type RM Length L Ch R = 1 ,91439   ,468,468,468
BEGIN DESCRIPTION:
Cypress Creek 141.0
END DESCRIPTION:
XS GIS Cut Line= 3
      1954725.03     13942425.03        1954375.       13942025.
      1954275.05     13941925.05
#Sta/Elev= 30
  4463.4 1929.12  4533.7 1916.41  4542.8 1911.82  4561.7 1904.71  4576.3 1891.83
  4608.2 1874.44  4635.8 1865.13  4657.1 1862.67  4676.2 1862.13  4795.9 1861.38
  4818.6 1860.62  4852.7 1855.12  4900.5 1854.54  4927.1 1851.72  4967.5 1850.59
  4990.8 1848.53  5015.9 1842.83  5016.3 1842.33    5021 1842.83    5026 1843.33
  5038.7 1848.04  5050.2 1857.86  5053.3 1859.32  5055.7 1864.48  5058.7 1874.63
  5061.8 1882.17  5065.1 1886.84  5076.9 1896.69  5111.8 1913.41  5136.3  1922.5
#Mann= 4 ,-1 , 0
  4463.4     .07       0  4795.9    .035       0  5015.9    .035       0
    5021     .07       0
Bank Sta=5015.9,5021
XS Rating Curve= 0 ,0
Exp/Cntr=0.3,0.1

Type RM Length L Ch R = 1 ,90971   ,447,447,447
BEGIN DESCRIPTION:
Cypress Creek 140.0
END DESCRIPTION:
XS GIS Cut Line= 3
      1954924.99     13942174.99        1954775.       13941825.
      1954625.01     13941575.02
#Sta/Elev= 30
  4623.4 1909.06  4665.4 1903.88  4679.9 1899.05  4686.4 1894.19    4693 1891.03
    4702 1880.97  4720.3 1866.38  4741.9 1853.91    4755 1849.01  4777.8  1847.4
  4829.9 1847.64  4857.5  1846.5  4955.6 1843.63  4970.4 1842.06  4983.4 1839.12
  4997.2 1838.69  4997.6 1838.19  5002.3 1838.69  5031.2 1845.02  5053.9 1855.32
  5060.4 1856.96  5086.7 1858.78  5111.4 1863.99  5141.3 1877.29  5176.3 1897.08
  5216.4 1917.68    5231 1923.57  5240.9 1928.79  5270.4 1937.71  5295.7 1941.42
#Mann= 5 ,-1 , 0
  4623.4     .07       0  4857.5    .035       0  4997.2    .035       0
  5002.3    .035       0  5031.2     .07       0
Bank Sta=4997.2,5002.3
XS Rating Curve= 0 ,0
Exp/Cntr=0.3,0.1

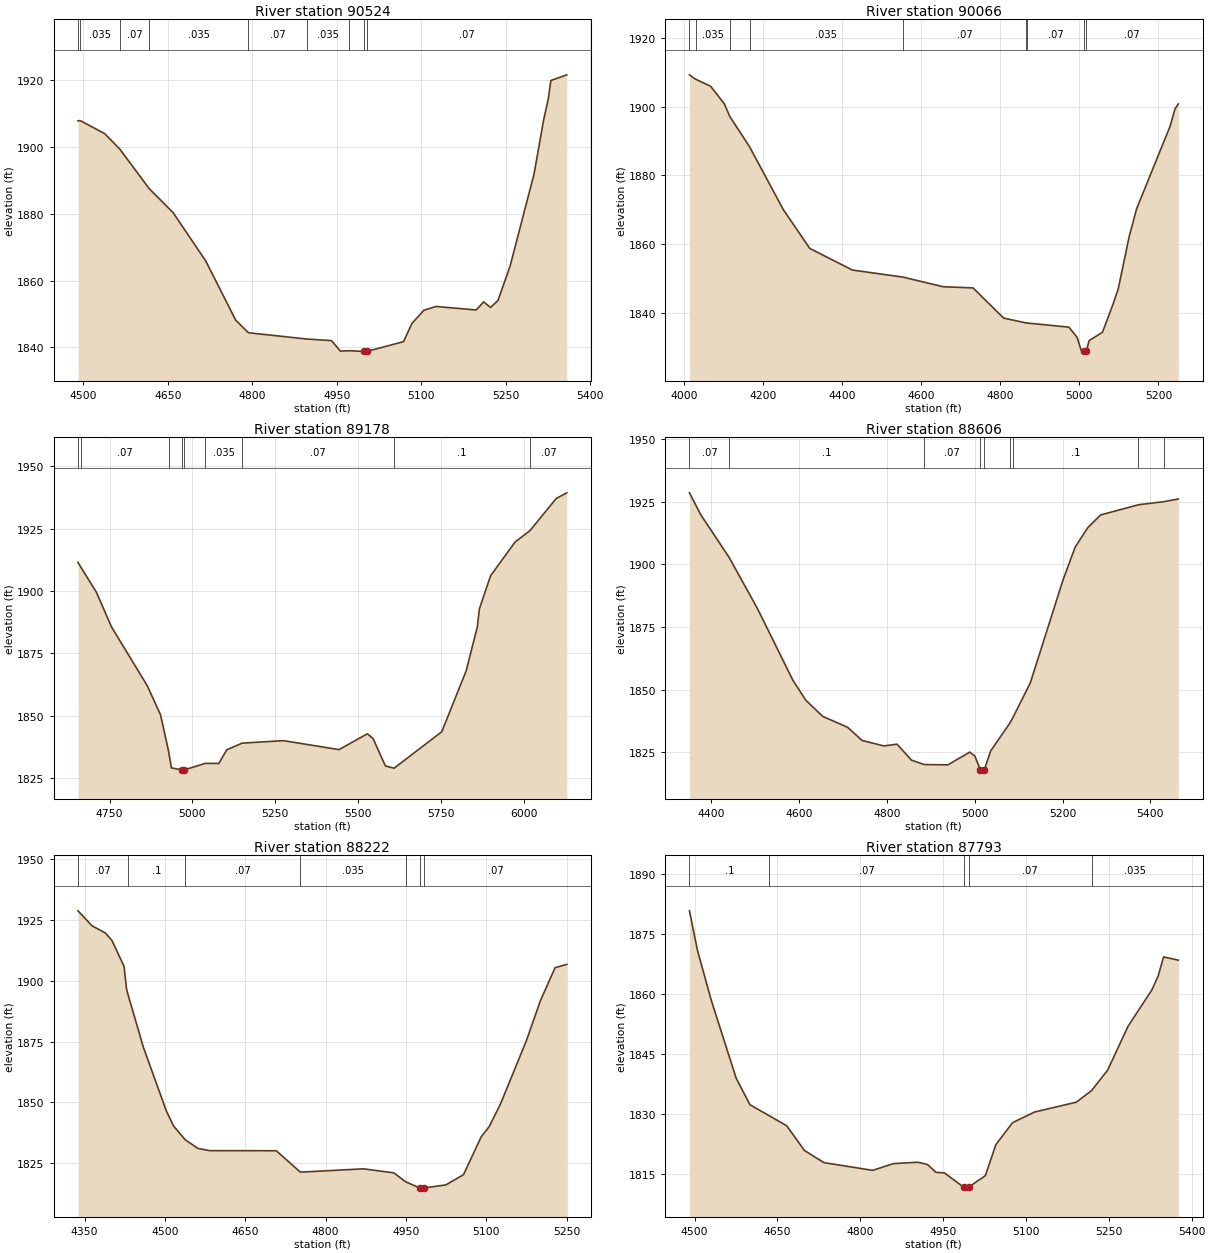
Type RM Length L Ch R = 1 ,90524   ,458,458,458
BEGIN DESCRIPTION:
Cypress Creek 139.0
END DESCRIPTION:
XS GIS Cut Line= 4
      1955036.35      13942144.8      1955209.32     13941781.51
        1955175.       13941675.      1954925.01     13941425.01
#Sta/Elev= 30
  4490.6 1907.88  4494.4 1907.98  4537.9 1904.08  4564.9 1899.42    4617 1887.58
  4659.5 1880.38  4717.4 1865.91  4770.5 1848.18  4793.2 1844.38  4896.5  1842.5
  4940.7 1842.02  4956.5 1838.87  4971.8 1838.99  4998.1 1838.77  4998.5 1838.27
  5003.2 1838.77  5068.6 1841.71  5083.5 1847.17  5104.7 1851.13  5126.4 1852.25
  5197.6  1851.2  5210.8 1853.64    5223 1851.97  5236.2 1854.02  5257.9 1864.44
  5300.4 1892.05  5317.3 1908.17  5325.8 1914.65  5330.1 1919.99  5358.4 1921.69
#Mann= 9 ,-1 , 0
  4490.6     .07       0  4494.4    .035       0  4564.9     .07       0
    4617    .035       0  4793.2     .07       0  4896.5    .035       0
  4971.8     .07       0  4998.1     .05       0  5003.2     .07       0
Bank Sta=4998.1,5003.2
XS Rating Curve= 0 ,0
Exp/Cntr=0.3,0.1

Type RM Length L Ch R = 1 ,90066   ,888,888,888
BEGIN DESCRIPTION:
Cypress Creek 138.0
END DESCRIPTION:
XS GIS Cut Line= 5
      1955044.91     13942170.83      1955354.55     13941780.04
      1955465.26      13941526.3        1955425.       13941325.
      1955174.97     13941274.99
#Sta/Elev= 30
  4014.6 1909.24  4029.9 1907.98  4067.9 1905.93  4102.4 1900.86  4116.8 1897.09
  4166.6 1888.29  4251.6 1870.06  4318.7 1858.72  4426.5 1852.43  4554.1 1850.38
  4656.1 1847.57  4731.4 1847.23  4808.8 1838.45  4865.8 1837.03  4867.1 1837.02
  4973.9 1835.81  4994.6 1832.84  5004.8 1829.08  5012.5 1828.75  5012.8 1828.25
  5017.6 1828.75  5025.1 1831.91  5058.8 1834.34  5086.3 1842.78  5098.6 1846.98
  5126.1 1862.12  5145.1 1870.29  5230.1 1894.41  5241.9 1899.31  5250.3 1900.75
#Mann= 9 ,-1 , 0
  4014.6     .07       0  4029.9    .035       0  4116.8     .07       0
  4166.6    .035       0  4554.1     .07       0  4865.8      .1       0
  4867.1     .07       0  5012.5     .05       0  5017.6     .07       0
Bank Sta=5012.5,5017.6
XS Rating Curve= 0 ,0
Exp/Cntr=0.3,0.1

Type RM Length L Ch R = 1 ,89178   ,572,572,572
BEGIN DESCRIPTION:
Cypress Creek 137.0
END DESCRIPTION:
XS GIS Cut Line= 5
      1956155.68     13941502.13      1956062.87     13941286.92
      1955911.82     13941200.98      1955292.03     13940859.84
      1954940.51     13940779.12
#Sta/Elev= 30
  4654.4 1911.53  4663.6 1909.51    4710 1899.54  4755.6 1885.63  4863.6 1862.04
  4903.9  1850.3  4927.9 1835.83  4936.4 1829.08  4967.8 1828.26  4968.3 1827.76
  4975.5 1828.26  5039.3 1830.89  5079.8 1830.83  5103.7 1836.31  5150.1 1838.99
    5275 1839.99  5442.7 1836.39  5528.4 1842.74  5545.6 1840.84  5582.9 1829.84
  5609.2 1828.94  5753.1 1843.56  5826.7 1867.94  5860.6 1885.66  5866.8 1892.89
  5900.6 1906.16  5974.5 1919.69  6019.9 1924.31  6098.8 1937.16  6130.7 1939.43
#Mann= 9 ,-1 , 0
  4654.4      .1       0  4663.6     .07       0  4927.9      .1       0
  4967.8     .05       0  4975.5      .1       0  5039.3    .035       0
  5150.1     .07       0  5609.2      .1       0  6019.9     .07       0
Bank Sta=4967.8,4975.5
XS Rating Curve= 0 ,0
Exp/Cntr=0.3,0.1

Type RM Length L Ch R = 1 ,88606   ,384,384,384
BEGIN DESCRIPTION:
Cypress Creek 136.0
END DESCRIPTION:
XS GIS Cut Line= 3
      1956613.15     13941014.44      1956025.11     13940741.82
      1955583.42     13940599.86
#Sta/Elev= 30
  4351.3 1928.52  4377.1 1919.75  4441.7 1902.69  4506.1 1882.27  4586.9 1853.61
  4616.2 1845.69  4654.6 1839.27  4711.1 1834.93  4744.1 1829.66  4793.7 1827.49
  4823.5 1828.18  4856.6  1821.8  4885.3 1820.06  4939.2 1819.93    4989 1825.01
  5000.4 1823.51  5013.2 1817.93  5013.7 1817.43  5022.1 1817.93  5036.6  1825.5
  5080.7 1836.72  5086.8 1838.66  5126.7 1852.63  5201.3 1893.79  5228.8 1906.85
  5257.2 1914.55  5286.5 1919.68  5372.9 1923.76  5430.1 1924.98  5463.4 1926.05
#Mann= 9 ,-1 , 0
  4351.3     .07       0  4441.7      .1       0  4885.3     .07       0
  5013.2     .05       0  5022.1     .07       0  5080.7     .07       0
  5086.8      .1       0  5372.9     .07       0  5430.1      .1       0
Bank Sta=5013.2,5022.1
XS Rating Curve= 0 ,0
Exp/Cntr=0.3,0.1

Type RM Length L Ch R = 1 ,88222   ,429,429,429
BEGIN DESCRIPTION:
Cypress Creek 135.0
END DESCRIPTION:
XS GIS Cut Line= 3
      1956722.99     13940709.36        1956125.       13940425.
      1955874.96       13940425.
#Sta/Elev= 30
  4337.8 1928.67  4364.1 1922.52    4389 1919.56  4401.3 1916.47  4423.8 1905.86
  4428.3 1896.88  4430.3 1894.94  4459.8 1872.69  4502.6 1846.59  4516.1 1840.37
  4537.9  1834.7  4561.7 1831.14  4583.6 1830.22  4707.9 1830.19  4752.8  1821.4
  4870.7 1822.76  4927.2 1821.11  4949.4 1817.43  4975.4 1814.93  4975.9 1814.43
  4984.3 1814.93  5024.2 1816.16  5057.2 1820.34  5090.2 1835.85  5105.2 1840.09
  5126.3 1849.39  5174.2 1875.13  5201.2 1892.02  5228.2 1905.33    5250 1906.69
#Mann= 7 ,-1 , 0
  4337.8     .07       0  4430.3      .1       0  4537.9     .07       0
  4752.8    .035       0  4949.4     .07       0  4975.4     .05       0
  4984.3     .07       0
Bank Sta=4975.4,4984.3
XS Rating Curve= 0 ,0
Exp/Cntr=0.3,0.1

Type RM Length L Ch R = 1 ,87793   ,521,521,521
BEGIN DESCRIPTION:
Cypress Creek 134.0
END DESCRIPTION:
XS GIS Cut Line= 3
      1956724.97     13940324.98      1956291.16     13940057.44
        1955925.       13939975.
#Sta/Elev= 30
  4490.8 1880.79  4505.2 1870.94  4529.8 1858.62  4575.2 1838.94  4600.3 1832.25
  4634.9 1829.52  4666.8 1826.99    4699 1820.79  4734.3 1817.75  4822.4 1815.82
  4860.3 1817.51  4904.4 1817.85  4921.8 1817.28  4937.1 1815.32  4952.4 1815.18
  4987.2 1811.62  4987.7 1811.12  4996.2 1811.62  5026.5 1814.49  5045.5 1822.24
  5075.7 1827.75  5115.7 1830.43  5191.1 1832.88  5218.9  1835.8  5247.9  1840.9
  5284.8 1851.88  5327.9 1860.96  5339.2  1864.4  5349.2 1869.24  5375.8 1868.45
#Mann= 5 ,-1 , 0
  4490.8      .1       0  4634.9     .07       0  4987.2     .05       0
  4996.2     .07       0  5218.9    .035       0
Bank Sta=4987.2,4996.2
XS Rating Curve= 0 ,0
Exp/Cntr=0.3,0.1