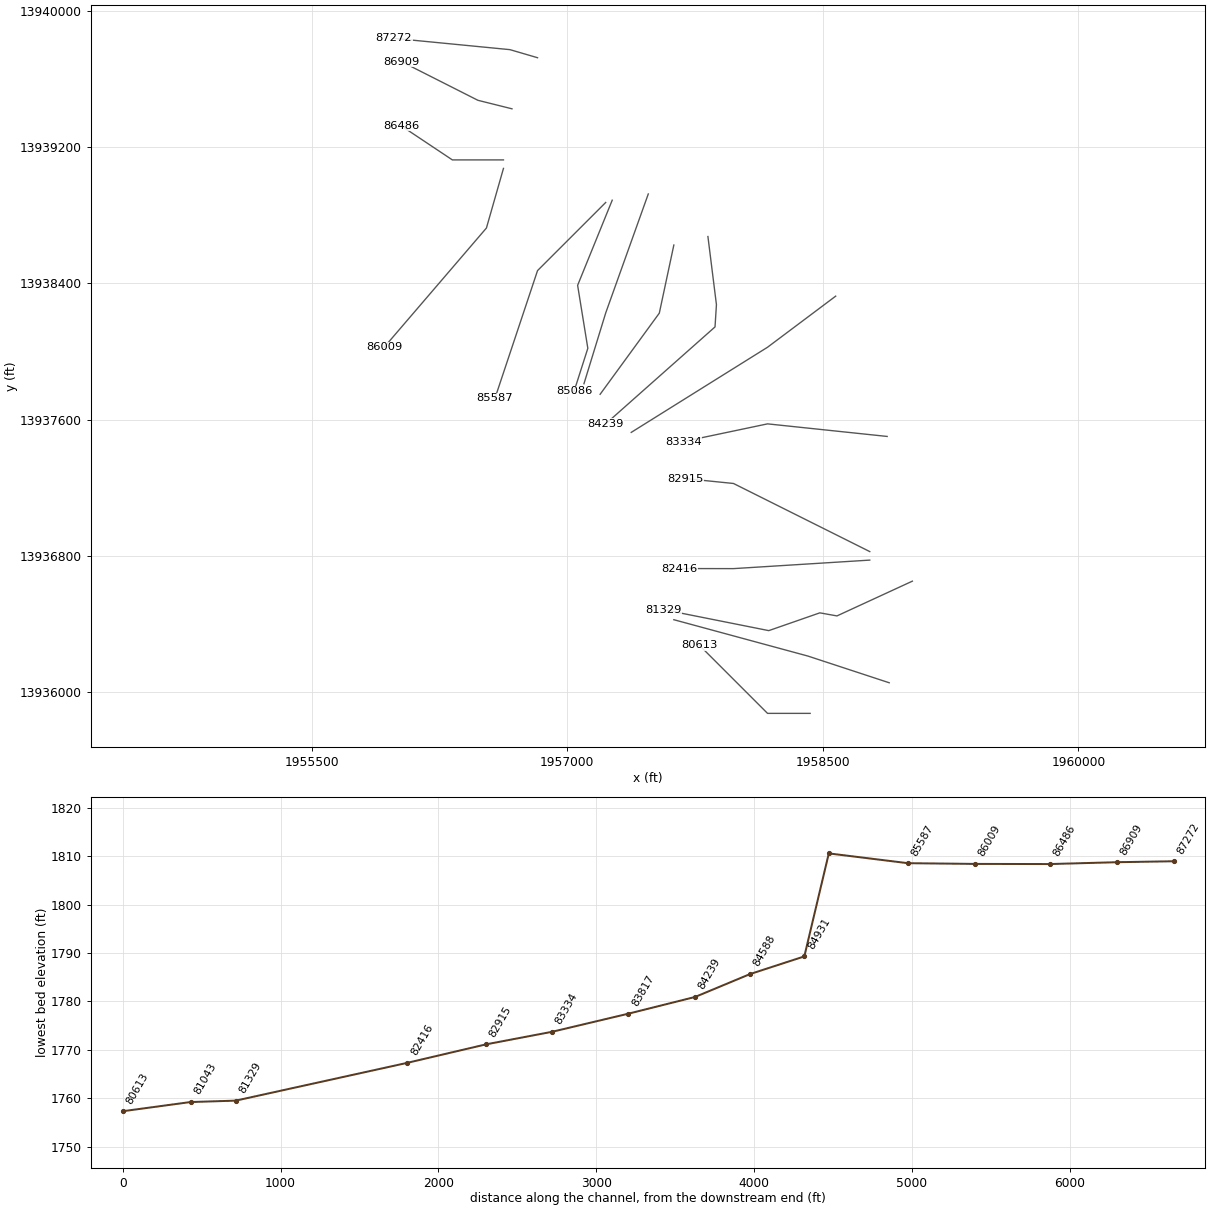
HEC-RAS study Cypress Creek.prj: Cypress Creek Base Level Engineering

--- Cypress Creek.g01 (geometry) --- (continued)

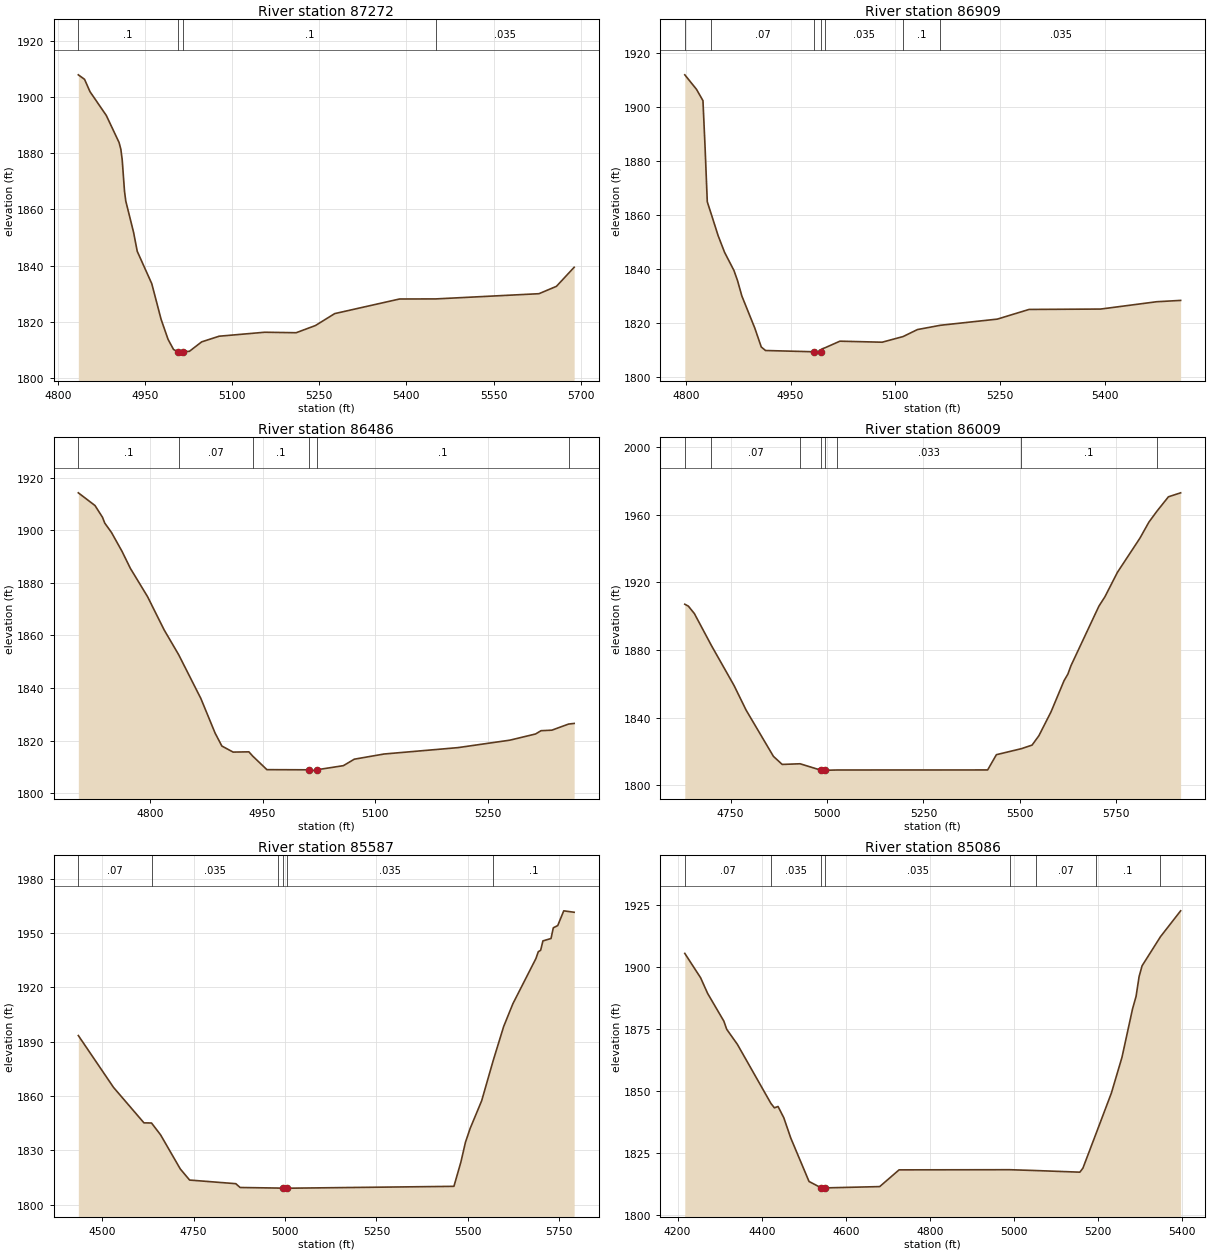
Type RM Length L Ch R = 1 ,87272   ,363,363,363
BEGIN DESCRIPTION:
Cypress Creek 133.0
END DESCRIPTION:
XS GIS Cut Line= 3
      1956825.02       13939725.      1956663.26     13939772.37
      1955981.54     13939838.84
#Sta/Elev= 30
  4835.3 1907.84    4846 1906.24  4855.4 1901.85  4883.5 1893.39  4905.4 1883.81
  4908.5 1881.39  4910.8 1877.68  4914.8 1866.47    4917 1862.98  4930.4 1851.88
  4936.7 1845.15  4961.7 1833.65  4977.8 1820.96  4989.8 1813.84  4999.2 1810.27
  5006.7 1809.47  5007.2 1808.97  5016.1 1809.47  5026.5 1809.61  5047.6 1812.97
  5077.7 1814.98  5156.1 1816.39  5210.3 1816.22  5243.5 1818.78  5276.6 1823.01
  5388.2  1828.2  5450.8 1828.23  5628.2 1830.08  5658.3  1832.7  5688.8 1839.47
#Mann= 4 ,-1 , 0
  4835.3      .1       0  5006.7     .05       0  5016.1      .1       0
  5450.8    .035       0
Bank Sta=5006.7,5016.1
XS Rating Curve= 0 ,0
Exp/Cntr=0.3,0.1

Type RM Length L Ch R = 1 ,86909   ,423,423,423
BEGIN DESCRIPTION:
Cypress Creek 132.0
END DESCRIPTION:
XS GIS Cut Line= 3
      1956674.99       13939425.        1956475.       13939475.
      1956025.55     13939702.52
#Sta/Elev= 30
  4798.5 1911.97  4815.2 1906.61  4824.5  1902.4  4827.6 1884.67  4830.7 1864.88
    4836 1860.64  4846.2 1852.35  4855.4 1846.18  4868.9  1839.4    4874 1835.67
  4880.2 1829.95  4898.7 1818.07    4908 1811.05  4914.1 1809.74  4983.7 1809.27
  4984.2 1808.77  4992.6 1808.77  4993.1 1809.27  4994.6  1810.3  4999.3 1810.76
  5020.6  1813.2  5081.1 1812.82  5111.1 1814.92  5131.6 1817.51  5164.6  1819.1
  5245.9 1821.38  5291.4 1824.97  5393.9 1825.11  5474.2 1827.83  5508.4 1828.32
#Mann= 7 ,-1 , 0
  4798.5      .1       0    4836     .07       0  4983.7     .05       0
  4993.1     .07       0  4999.3    .035       0  5111.1      .1       0
  5164.6    .035       0
Bank Sta=4983.7,4993.1
XS Rating Curve= 0 ,0
Exp/Cntr=0.3,0.1

Type RM Length L Ch R = 1 ,86486   ,477,477,477
BEGIN DESCRIPTION:
Cypress Creek 131.0
END DESCRIPTION:
XS GIS Cut Line= 3
      1956624.96       13939125.        1956325.       13939125.
      1956025.02     13939324.99
#Sta/Elev= 30
  4704.6 1914.27  4726.8 1909.44  4736.8 1904.96  4739.8 1902.76  4748.8 1899.17
  4762.8 1892.01  4773.9 1885.55  4796.8 1874.78  4818.9 1862.13  4838.3 1852.66
  4867.8 1836.04  4886.8 1822.86  4895.8 1817.94  4910.8 1815.63  4931.8 1815.73
  4936.9 1814.11  4955.8 1808.95  5012.5 1808.89    5013 1808.39    5022 1808.89
  5057.7 1810.47  5072.2 1812.93  5111.8  1814.9  5210.3 1817.33  5279.5 1820.17
  5313.7 1822.52    5321 1823.77  5335.4 1823.97  5357.6 1826.29  5365.1 1826.54
#Mann= 6 ,-1 , 0
  4704.6      .1       0  4838.3     .07       0  4936.9      .1       0
  5012.5     .05       0    5022      .1       0  5357.6    .035       0
Bank Sta=5012.5,5022
XS Rating Curve= 0 ,0
Exp/Cntr=0.3,0.1

Type RM Length L Ch R = 1 ,86009   ,422,422,422
BEGIN DESCRIPTION:
Cypress Creek 130.0
END DESCRIPTION:
XS GIS Cut Line= 3
      1956624.99     13939074.97        1956525.       13938725.
      1955925.02     13938025.03
#Sta/Elev= 30
    4631 1907.11  4640.3 1905.98  4655.9 1901.58  4699.9 1882.76  4758.8 1859.03
    4790 1844.51  4860.9 1817.14  4883.6 1812.38    4930 1812.77  4984.8 1808.92
  4985.3 1808.42  4994.6 1808.92  5026.2 1809.09  5416.4 1809.12  5439.1 1818.14
    5504  1821.7  5531.6 1823.81  5549.4 1829.39    5581 1843.58  5614.6 1861.92
  5624.5 1865.79  5632.4 1870.72    5705 1905.99  5720.6 1911.54  5752.9 1925.94
  5811.4 1946.21  5834.8 1955.73  5855.3 1962.09  5885.3 1970.65  5916.9    1973
#Mann= 8 ,-1 , 0
    4631      .1       0  4699.9     .07       0    4930      .1       0
  4984.8     .05       0  4994.6      .1       0  5026.2    .033       0
    5504      .1       0  5855.3     .07       0
Bank Sta=4984.8,4994.6
XS Rating Curve= 0 ,0
Exp/Cntr=0.3,0.1

Type RM Length L Ch R = 1 ,85587   ,501,501,501
BEGIN DESCRIPTION:
Cypress Creek 129.0
END DESCRIPTION:
XS GIS Cut Line= 3
      1957224.97     13938874.97        1956825.       13938475.
        1956575.     13937725.01
#Sta/Elev= 30
  4434.6 1893.42  4531.1 1864.71  4614.1 1845.18  4634.8  1845.1  4659.6 1838.55
  4713.5 1819.71    4739 1813.58  4865.3 1811.58  4877.1 1809.47  4981.5 1809.16
  4995.2 1809.07  4995.7 1808.57  5005.2 1809.07  5461.9 1810.11  5480.9 1823.44
  5493.5 1834.48  5506.2 1842.04  5537.8 1857.39  5569.5  1879.7  5597.9 1898.36
  5623.2 1910.99  5686.4 1936.04  5692.7 1939.74  5699.1  1940.5  5705.4 1945.71
  5727.5 1947.03  5733.8 1952.95  5745.9 1954.18  5762.3 1962.32  5790.8 1961.53
#Mann= 6 ,-1 , 0
  4434.6     .07       0  4634.8    .035       0  4981.5    .035       0
  4995.2    .035       0  5005.2    .035       0  5569.5      .1       0
Bank Sta=4995.2,5005.2
XS Rating Curve= 0 ,0
Exp/Cntr=0.3,0.1

Type RM Length L Ch R = 1 ,85086   ,155,155,155
BEGIN DESCRIPTION:
Cypress Creek 129.1
END DESCRIPTION:
XS GIS Cut Line= 4
      1957263.37     13938888.44      1957060.26     13938388.48
      1957120.16     13938018.69      1957039.44     13937766.13
#Sta/Elev= 30
  4217.1 1905.67  4254.7 1895.84  4271.5  1889.5    4310 1878.35  4316.8 1875.06
  4342.2 1868.98  4421.9 1845.18  4430.2 1843.38  4438.9 1843.92  4452.6 1839.38
    4469 1831.27  4512.6 1813.68  4541.7 1811.09  4542.2 1810.59  4551.7 1811.09
  4680.7 1811.61  4726.8 1818.36  4990.3 1818.42  5052.5 1818.08  5156.8 1817.43
    5164 1819.02  5194.8 1832.76  5231.8 1849.34    5257 1863.76  5282.1 1883.27
  5290.5 1888.33  5297.7 1896.29  5304.8 1900.66  5348.6 1912.41  5396.5 1922.84
#Mann= 8 ,-1 , 0
  4217.1     .07       0  4421.9    .035       0  4541.7    .035       0
  4551.7    .035       0  4990.3    .033       0  5052.5     .07       0
  5194.8      .1       0  5348.6     .07       0
Bank Sta=4541.7,4551.7
XS Rating Curve= 0 ,0
Exp/Cntr=0.3,0.1

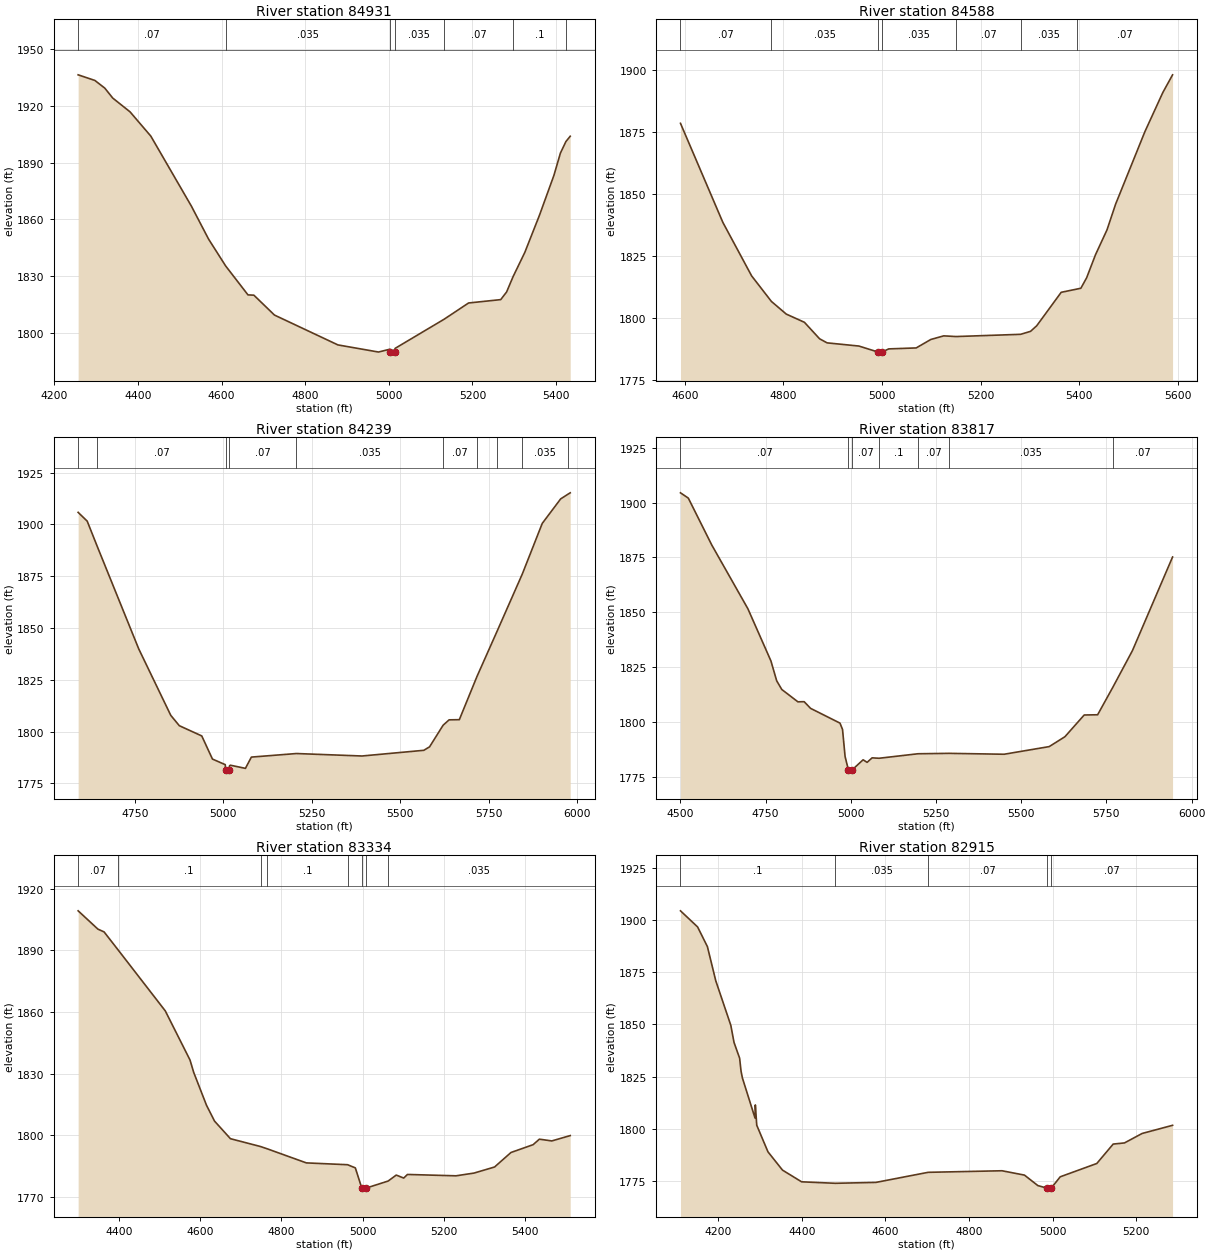
Type RM Length L Ch R = 1 ,84931   ,343,343,343
BEGIN DESCRIPTION:
Cypress Creek 128.0
END DESCRIPTION:
XS GIS Cut Line= 3
      1957475.01     13938925.03      1957225.48     13938227.42
      1957097.42     13937810.64
#Sta/Elev= 30
  4257.1 1936.39  4297.2 1933.41  4320.8 1929.37  4339.9  1924.1  4381.3 1916.81
  4430.9    1904  4527.9 1867.01  4569.1 1849.56    4610 1835.35  4663.3 1820.09
  4677.4 1819.94  4726.6 1809.43  4878.4 1793.65  4975.4 1789.89  5002.6 1791.37
  5003.8 1789.81  5004.3 1789.31  5013.8 1789.81  5015.1 1791.81  5132.3 1807.21
  5190.9 1815.81  5267.8 1817.59  5281.9 1821.65  5297.3 1829.71  5325.4 1842.54
  5360.3  1862.1  5394.9 1883.19  5410.6 1895.05  5423.7 1901.13    5434 1903.93
#Mann= 7 ,-1 , 0
  4257.1     .07       0    4610    .035       0  5003.8    .035       0
  5013.8    .035       0  5132.3     .07       0  5297.3      .1       0
  5423.7     .07       0
Bank Sta=5003.8,5013.8
XS Rating Curve= 0 ,0
Exp/Cntr=0.3,0.1

Type RM Length L Ch R = 1 ,84588   ,349,349,349
BEGIN DESCRIPTION:
Cypress Creek 127.0
END DESCRIPTION:
XS GIS Cut Line= 3
      1957625.01     13938625.04      1957539.69     13938225.11
      1957192.36     13937748.71
#Sta/Elev= 30
    4591 1878.55  4676.9 1838.54  4735.3 1816.91  4775.5 1806.56  4805.7 1801.44
  4842.5 1798.13  4873.2 1791.47  4888.5 1789.82    4953 1788.53  4990.9 1786.17
  4991.4 1785.67  5000.9 1786.17  5013.5 1787.38  5069.3 1787.77    5099 1791.19
  5125.2 1792.65  5150.2 1792.37  5281.1 1793.27  5301.3 1794.47  5313.9 1796.74
  5363.5 1810.25  5394.7 1811.53  5403.4 1811.89  5415.1  1816.1  5433.1 1825.43
  5456.4 1835.46    5474 1845.92  5533.4  1875.2  5569.7 1890.98  5589.5 1898.15
#Mann= 7 ,-1 , 0
    4591     .07       0  4775.5    .035       0  4990.9    .035       0
  5000.9    .035       0  5150.2     .07       0  5281.1    .035       0
  5394.7     .07       0
Bank Sta=4990.9,5000.9
XS Rating Curve= 0 ,0
Exp/Cntr=0.3,0.1

Type RM Length L Ch R = 1 ,84239   ,422,422,422
BEGIN DESCRIPTION:
Cypress Creek 126.0
END DESCRIPTION:
XS GIS Cut Line= 4
        1957825.     13938675.04        1957875.       13938275.
      1957866.72     13938144.26      1957225.06     13937575.05
#Sta/Elev= 30
  4589.2 1905.81  4614.8 1901.58  4643.7 1889.19  4760.5 1839.96  4851.2 1807.85
  4875.4 1802.85  4938.9 1797.91  4969.1 1786.75  5005.3 1784.06  5006.3 1781.43
  5006.8 1780.93  5016.4 1781.43  5017.3 1783.49  5019.9 1783.79  5062.4 1782.26
  5079.2  1787.7  5206.6 1789.42    5392 1788.23  5567.1 1790.98  5583.3 1792.67
  5621.5 1803.07  5638.5 1805.68  5667.4 1805.76  5717.6 1826.71  5775.2 1848.81
  5845.8 1876.15    5902 1900.49    5954  1912.3  5973.9 1914.48  5981.1 1915.24
#Mann= 10 ,-1 , 0
  4589.2    .035       0  4643.7     .07       0  5006.3     .05       0
  5016.4     .07       0  5206.6    .035       0  5621.5     .07       0
  5717.6    .035       0  5775.2     .07       0  5845.8    .035       0
  5973.9     .07       0
Bank Sta=5006.3,5016.4
XS Rating Curve= 0 ,0
Exp/Cntr=0.3,0.1

Type RM Length L Ch R = 1 ,83817   ,483,483,483
BEGIN DESCRIPTION:
Cypress Creek 125.0
END DESCRIPTION:
XS GIS Cut Line= 3
      1958574.96     13938324.97        1958175.       13938025.
      1957374.96     13937524.97
#Sta/Elev= 30
  4500.6 1904.44  4523.6 1902.02  4592.1 1880.71  4698.4 1851.53  4765.9 1827.75
  4782.8 1818.68  4797.8 1814.72    4845  1809.1  4863.4 1809.16  4882.1 1806.12
  4968.4 1799.39  4975.9  1796.5  4983.4 1784.17  4993.2 1777.98  4993.7 1777.48
  5003.6 1777.98  5036.3 1782.65    5048 1781.48  5062.7 1783.54  5083.1 1783.35
  5197.1  1785.4  5288.9 1785.59  5449.9 1785.18  5582.2 1788.67  5628.2 1793.17
  5684.8 1803.09  5724.2 1803.19  5768.7 1815.71  5826.3 1832.46    5944 1875.16
#Mann= 7 ,-1 , 0
  4500.6     .07       0  4993.2     .05       0  5003.6     .07       0
  5083.1      .1       0  5197.1     .07       0  5288.9    .035       0
  5768.7     .07       0
Bank Sta=4993.2,5003.6
XS Rating Curve= 0 ,0
Exp/Cntr=0.3,0.1

Type RM Length L Ch R = 1 ,83334   ,419,419,419
BEGIN DESCRIPTION:
Cypress Creek 124.0
END DESCRIPTION:
XS GIS Cut Line= 3
      1958876.91     13937501.15        1958175.       13937575.
      1957679.33      13937470.7
#Sta/Elev= 30
  4299.1 1909.21  4347.9 1900.29    4363 1898.95    4397 1890.33  4513.8  1860.5
  4574.7 1836.59  4583.8 1830.56  4615.2 1814.63  4635.1 1806.86  4674.3 1798.29
  4748.5 1794.47  4765.3 1793.34  4861.3 1786.51    4963 1785.62    4982 1784.08
  4997.9 1774.24  4998.4 1773.74  5008.4 1774.24  5062.9 1777.68  5082.8 1780.58
  5101.2 1779.13  5110.4 1780.88    5230 1780.22  5274.4 1781.55    5325 1784.51
  5365.5 1791.58    5420 1795.38  5435.4 1798.06    5466  1797.2  5511.4  1799.8
#Mann= 8 ,-1 , 0
  4299.1     .07       0    4397      .1       0  4748.5     .07       0
  4765.3      .1       0    4963     .07       0  4997.9     .05       0
  5008.4     .07       0  5062.9    .035       0
Bank Sta=4997.9,5008.4
XS Rating Curve= 0 ,0
Exp/Cntr=0.3,0.1

Type RM Length L Ch R = 1 ,82915   ,499,499,499
BEGIN DESCRIPTION:
Cypress Creek 123.0
END DESCRIPTION:
XS GIS Cut Line= 3
      1958774.96     13936825.02        1957975.       13937225.
      1957693.33     13937253.59
#Sta/Elev= 30
  4109.7 1904.33  4150.6 1896.63  4174.1  1887.2  4194.2 1870.81  4230.1 1849.56
  4237.8 1841.36  4251.2  1833.8  4254.6 1827.62  4257.9 1824.32  4288.1 1805.15
  4288.8 1811.44  4292.2 1801.71    4319    1789  4353.8 1780.24  4399.5 1774.64
  4480.3 1773.93  4577.3 1774.36  4702.3 1779.18  4879.1 1779.93  4932.8 1777.85
  4964.8 1772.84  4986.4 1771.64  4986.9 1771.14  4996.9 1771.64  5018.4 1777.04
  5105.9 1783.41  5145.1  1792.7  5172.1 1793.25  5214.4 1797.78  5287.2 1801.68
#Mann= 5 ,-1 , 0
  4109.7      .1       0  4480.3    .035       0  4702.3     .07       0
  4986.4     .05       0  4996.9     .07       0
Bank Sta=4986.4,4996.9
XS Rating Curve= 0 ,0
Exp/Cntr=0.3,0.1

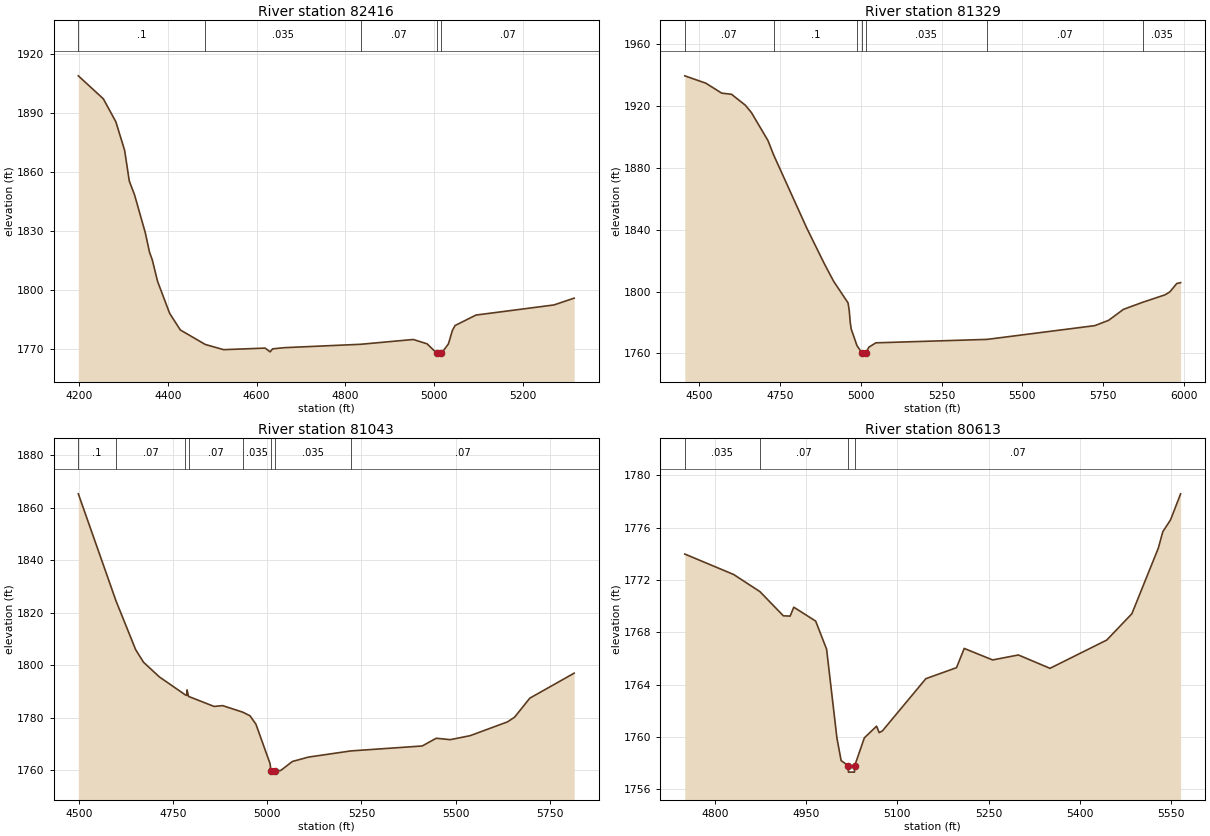
Type RM Length L Ch R = 1 ,82416   ,1087,1087,1087
BEGIN DESCRIPTION:
Cypress Creek 122.0
END DESCRIPTION:
XS GIS Cut Line= 3
      1958775.01       13936775.        1957975.       13936725.
      1957659.47     13936725.44
#Sta/Elev= 30
  4198.4 1908.69  4254.7 1897.02  4282.9 1885.38  4302.7 1870.87  4313.2 1855.27
  4325.2 1848.12  4349.3 1828.97  4358.9 1819.01    4365 1815.24    4377 1804.23
  4404.1 1788.07  4428.1 1779.62  4484.3 1772.24  4525.8 1769.59  4619.2 1770.38
  4630.5 1768.48  4636.2    1770  4662.6  1770.6  4834.5 1772.32    4953 1774.76
  4984.1 1772.56  5005.9 1767.82  5006.4 1767.32  5016.6 1767.82  5032.2 1772.51
  5041.2 1779.36  5047.2 1781.85  5094.3 1787.16  5269.9  1792.3  5315.5 1795.76
#Mann= 5 ,-1 , 0
  4198.4      .1       0  4484.3    .035       0  4834.5     .07       0
  5005.9     .05       0  5016.6     .07       0
Bank Sta=5005.9,5016.6
XS Rating Curve= 0 ,0
Exp/Cntr=0.3,0.1

Type RM Length L Ch R = 1 ,81329   ,286,286,286
BEGIN DESCRIPTION:
Cypress Creek 121.1
END DESCRIPTION:
XS GIS Cut Line= 5
      1959025.06     13936651.43      1958582.37     13936447.27
      1958481.89      13936465.3       1958182.2     13936360.91
      1957564.99     13936484.03
#Sta/Elev= 30
  4454.6  1939.6  4520.2  1934.8  4568.8 1928.41  4599.4 1927.65  4642.3 1920.57
  4661.3 1915.74  4712.4 1897.67  4729.9 1888.41  4833.1 1840.83  4886.5 1818.21
  4915.6 1806.71  4960.5 1792.63  4964.1 1787.75  4967.1 1780.41  4970.2  1775.8
    4988 1765.04  5004.4 1760.01  5004.9 1759.51  5015.2 1760.01    5025 1764.02
  5046.5 1766.82  5391.3 1769.05    5725 1777.95  5767.8 1781.38  5813.7 1788.48
  5872.8 1793.02  5942.2 1797.85  5957.5 1799.77  5978.9  1805.2  5990.9 1805.78
#Mann= 7 ,-1 , 0
  4454.6     .07       0  4729.9      .1       0    4988    .035       0
  5004.4    .035       0  5015.2    .035       0  5391.3     .07       0
  5872.8    .035       0
Bank Sta=5004.4,5015.2
XS Rating Curve= 0 ,0
Exp/Cntr=0.3,0.1

Type RM Length L Ch R = 1 ,81043   ,430,430,430
BEGIN DESCRIPTION:
Cypress Creek 121.0
END DESCRIPTION:
XS GIS Cut Line= 3
      1958889.17     13936054.72      1958411.95     13936211.52
      1957625.01       13936425.
#Sta/Elev= 30
  4497.5 1865.24  4597.9 1824.35  4649.9 1805.87  4670.7 1801.09  4713.1 1795.47
  4781.6 1788.68  4785.7 1788.44  4786.4 1790.55  4790.3 1788.07  4858.2 1784.25
  4881.1 1784.55  4934.2 1782.08  4953.7 1780.69  4969.5 1777.48  5007.3 1762.35
  5008.9 1759.72  5009.4 1759.22  5019.7 1759.72  5035.3 1759.84  5066.3 1763.27
  5108.8 1764.94  5221.9  1767.3  5411.4 1769.18  5448.7 1772.13    5486 1771.59
  5538.8 1773.11  5638.3 1778.38  5656.9 1780.16  5697.3 1787.39  5815.2 1796.92
#Mann= 8 ,-1 , 0
  4497.5      .1       0  4597.9     .07       0  4781.6    .035       0
  4790.3     .07       0  4934.2    .035       0  5008.9    .035       0
  5019.7    .035       0  5221.9     .07       0
Bank Sta=5008.9,5019.7
XS Rating Curve= 0 ,0
Exp/Cntr=0.3,0.1

Type RM Length L Ch R = 1 ,80613   ,518,518,518
BEGIN DESCRIPTION:
Cypress Creek 120.0
END DESCRIPTION:
XS GIS Cut Line= 3
      1958425.04       13935875.        1958175.       13935875.
      1957775.02     13936274.98
#Sta/Elev= 30
  4750.3 1773.98  4830.6 1772.42  4873.9 1771.11  4912.5 1769.26  4923.6 1769.24
  4929.6 1769.92  4965.6 1768.86  4983.6 1766.71  5000.6 1759.92  5007.5  1758.2
    5019 1757.82  5019.5 1757.32  5029.4 1757.32  5029.9 1757.82  5045.7 1759.94
  5065.8 1760.83    5070 1760.34  5075.4 1760.47  5146.9 1764.46  5197.3  1765.3
    5210 1766.77  5256.7 1765.89  5299.1 1766.27  5351.1 1765.25  5444.5 1767.41
  5485.8 1769.42  5529.3 1774.43  5536.7 1775.69  5549.4 1776.59    5566 1778.58
#Mann= 4 ,-1 , 0
  4750.3    .035       0  4873.9     .07       0    5019     .05       0
  5029.9     .07       0
Bank Sta=5019,5029.9
XS Rating Curve= 0 ,0
Exp/Cntr=0.3,0.1