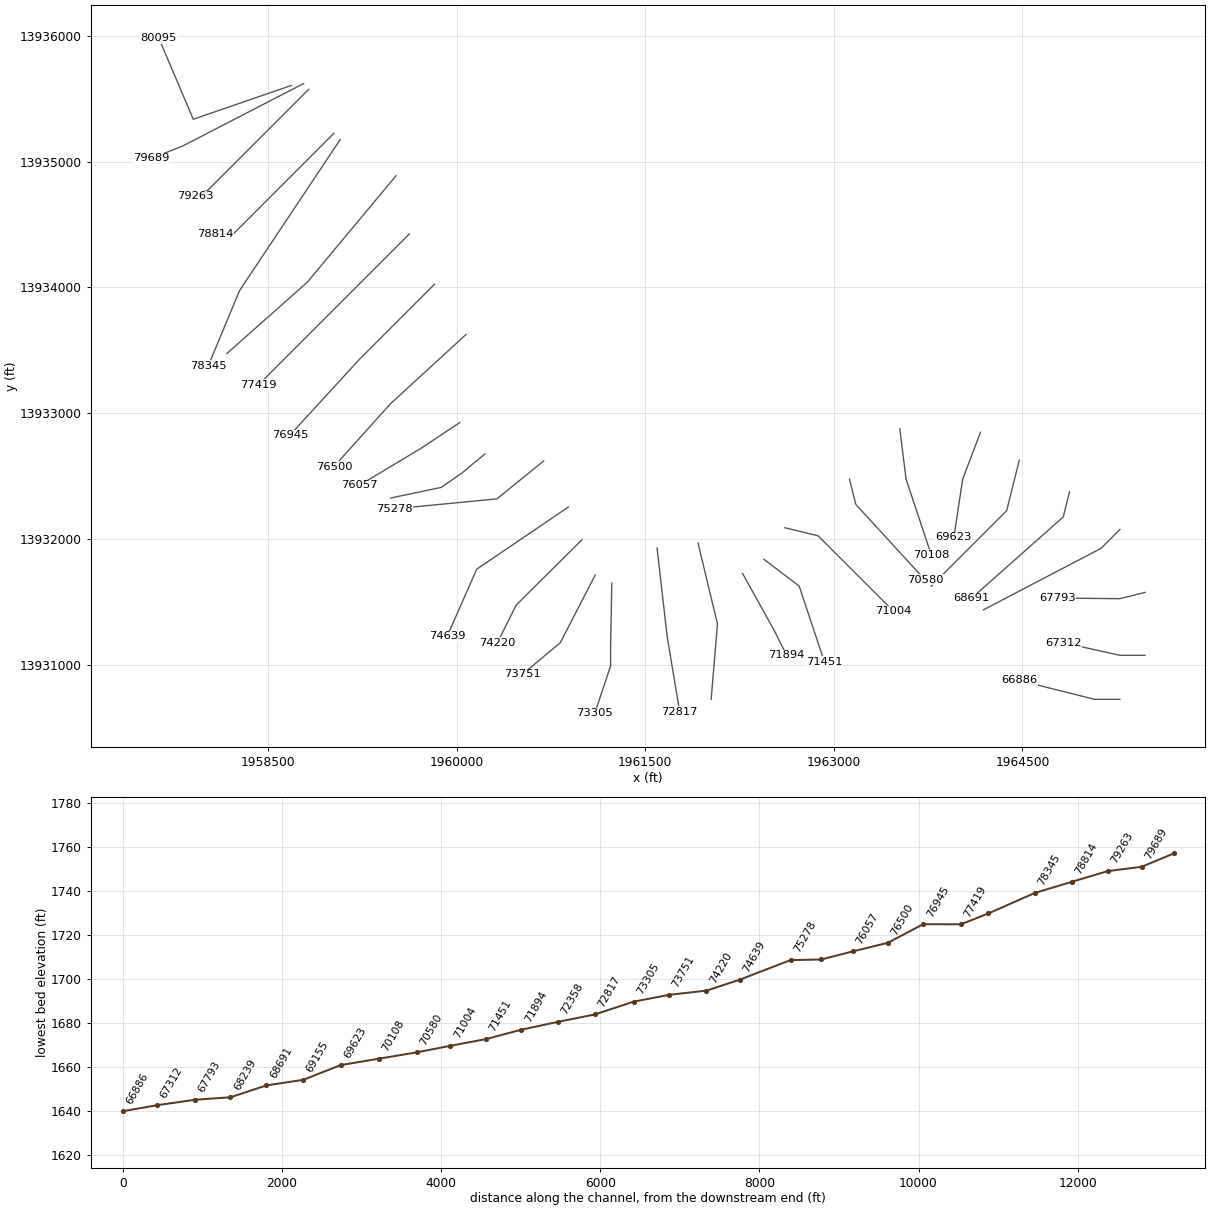
HEC-RAS study Cypress Creek.prj: Cypress Creek Base Level Engineering

--- Cypress Creek.g01 (geometry) --- (continued)

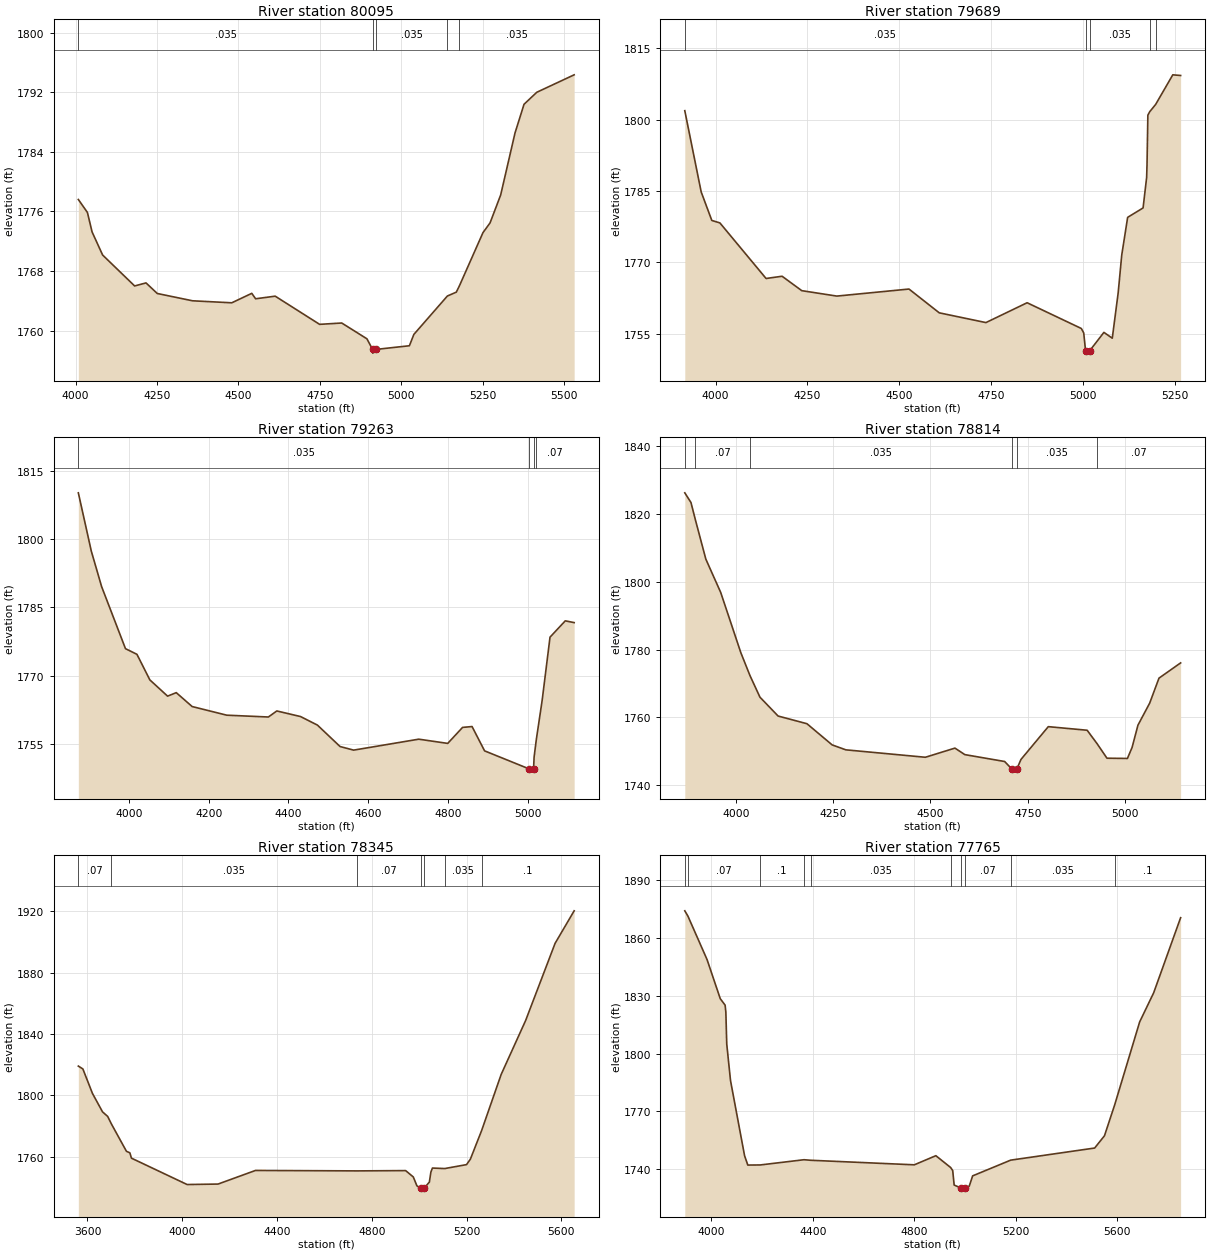
Type RM Length L Ch R = 1 ,80095   ,406,406,406
BEGIN DESCRIPTION:
Cypress Creek 119.1
END DESCRIPTION:
XS GIS Cut Line= 3
      1958685.26     13935604.63      1957906.62      13935336.4
      1957633.17     13935979.64
#Sta/Elev= 30
  4008.4 1777.61  4036.3 1775.87  4050.6 1773.26    4083 1770.16  4181.3 1766.01
  4216.2 1766.42  4250.8    1765    4359 1764.02  4479.6 1763.75    4541 1765.02
  4552.8 1764.29  4612.9 1764.64  4749.3 1760.86  4817.2 1761.04  4894.6 1758.92
  4911.9  1757.5  4912.4    1757  4922.9  1757.5    5025 1757.99  5038.7 1759.51
  5141.6 1764.66    5169 1765.18  5178.7 1766.04  5250.9 1773.16  5272.7 1774.47
  5305.3 1778.22  5349.3 1786.53    5377 1790.38  5416.2 1791.99  5530.9 1794.33
#Mann= 5 ,-1 , 0
  4008.4    .035       0  4911.9    .035       0  4922.9    .035       0
  5141.6     .07       0  5178.7    .035       0
Bank Sta=4911.9,4922.9
XS Rating Curve= 0 ,0
Exp/Cntr=0.3,0.1

Type RM Length L Ch R = 1 ,79689   ,426,426,426
BEGIN DESCRIPTION:
Cypress Creek 119.0
END DESCRIPTION:
XS GIS Cut Line= 3
      1958784.22     13935620.25        1957825.       13935125.
      1957574.98     13935024.99
#Sta/Elev= 30
  3916.3 1801.87  3960.9 1784.79  3989.8  1778.8  4011.8 1778.28  4137.4  1766.6
    4181 1767.07  4234.5 1764.04  4329.9  1762.9  4526.2 1764.38  4608.5 1759.38
  4735.5 1757.33  4847.5  1761.5    4995 1756.09  5001.5 1755.16  5006.5 1751.41
    5007 1750.91  5017.8 1751.41  5056.4 1755.27  5079.2 1754.05  5095.2 1763.57
  5104.9 1771.51    5121 1779.45    5163 1781.43  5172.7 1787.88  5173.7 1790.53
    5176 1800.94  5181.3 1801.68  5197.1 1803.18  5243.8 1809.41  5265.1 1809.27
#Mann= 5 ,-1 , 0
  3916.3    .035       0  5006.5    .035       0  5017.8    .035       0
  5181.3     .07       0  5197.1    .035       0
Bank Sta=5006.5,5017.8
XS Rating Curve= 0 ,0
Exp/Cntr=0.3,0.1

Type RM Length L Ch R = 1 ,79263   ,449,449,449
BEGIN DESCRIPTION:
Cypress Creek 118.0
END DESCRIPTION:
XS GIS Cut Line= 3
      1958824.99     13935574.99        1958025.       13934775.
      1957924.96     13934724.98
#Sta/Elev= 30
  3873.3 1810.21  3905.8 1797.39  3931.7 1789.57  3991.5 1775.92  4020.3 1774.67
  4052.6 1769.05  4097.1 1765.47  4118.8 1766.24  4158.7 1763.18  4245.4 1761.28
  4349.8 1760.88    4371 1762.21  4430.4 1760.98  4472.8  1759.1  4529.6 1754.38
  4563.6 1753.59  4726.9    1756  4799.5 1755.07  4836.7 1758.59  4860.5 1758.78
  4891.9 1753.43  5003.4 1749.47  5003.9 1748.97  5014.7 1749.47  5016.1 1752.07
  5021.7 1755.96  5036.1 1764.44    5056 1778.45  5094.2 1782.04  5116.5 1781.65
#Mann= 4 ,-1 , 0
  3873.3    .035       0  5003.4    .035       0  5014.7    .035       0
  5021.7     .07       0
Bank Sta=5003.4,5014.7
XS Rating Curve= 0 ,0
Exp/Cntr=0.3,0.1

Type RM Length L Ch R = 1 ,78814   ,469,469,469
BEGIN DESCRIPTION:
Cypress Creek 117.0
END DESCRIPTION:
XS GIS Cut Line= 3
      1959024.97     13935224.97        1958225.       13934425.
      1958082.03     13934425.29
#Sta/Elev= 30
  3868.7 1826.22  3884.6 1823.35  3895.6  1818.4  3922.8 1806.65    3961 1796.83
  4012.9    1779    4036 1772.36  4061.9 1765.93  4108.5 1760.37  4182.6 1758.11
  4247.4 1751.86  4282.5  1750.4    4487 1748.21    4563 1750.91  4588.4 1748.99
  4690.7 1746.96  4710.3 1744.62  4710.8 1744.12  4721.6 1744.62  4732.7 1747.57
  4802.9 1757.24  4902.8 1756.18  4928.4  1752.2  4953.7 1747.93  5006.3 1747.86
  5018.3 1751.12  5033.3 1757.67  5063.4 1764.16  5087.4 1771.55    5143 1776.05
#Mann= 6 ,-1 , 0
  3868.7    .035       0  3895.6     .07       0    4036    .035       0
  4710.3     .05       0  4721.6    .035       0  4928.4     .07       0
Bank Sta=4710.3,4721.6
XS Rating Curve= 0 ,0
Exp/Cntr=0.3,0.1

Type RM Length L Ch R = 1 ,78345   ,580,580,580
BEGIN DESCRIPTION:
Cypress Creek 116.0
END DESCRIPTION:
XS GIS Cut Line= 3
      1959075.01     13935175.01        1958275.       13933975.
      1958025.01     13933375.03
#Sta/Elev= 30
  3561.5 1819.12  3580.7 1817.25  3621.1 1801.32  3663.6 1789.32  3685.3 1786.35
  3701.2 1781.41  3764.6 1763.62    3779 1762.66  3785.5 1759.18  4020.6    1742
  4151.1 1742.31    4309 1751.17  4738.3 1750.88  4942.6 1751.07    4975 1746.92
  4990.2 1741.15  5006.7 1739.51  5007.2 1739.01  5020.1 1739.51  5042.7 1743.59
  5049.2 1750.11  5055.7 1752.73  5107.5  1752.4  5199.6 1754.97  5215.8 1758.53
  5263.2 1777.12  5345.8 1813.71  5448.9 1848.77  5573.3 1899.04  5653.7  1920.2
#Mann= 7 ,-1 , 0
  3561.5     .07       0  3701.2    .035       0  4738.3     .07       0
  5006.7     .05       0  5020.1     .07       0  5107.5    .035       0
  5263.2      .1       0
Bank Sta=5006.7,5020.1
XS Rating Curve= 0 ,0
Exp/Cntr=0.3,0.1

Type RM Length L Ch R = 1 ,77765   ,346,346,346
BEGIN DESCRIPTION:
Cypress Creek 115.0
END DESCRIPTION:
XS GIS Cut Line= 3
        1959519.     13934887.37      1958812.55     13934040.26
      1958174.98     13933474.98
#Sta/Elev= 30
  3895.7 1874.02  3907.9 1871.32  3983.4 1848.78  4035.5  1828.5  4054.7 1825.11
  4057.6  1821.5  4061.1 1804.99    4076 1786.03  4131.4 1747.08  4144.2 1742.23
  4193.2 1742.29  4365.7    1745  4392.1 1744.72  4800.7 1742.36  4885.7 1747.09
    4944 1740.96  4952.1 1739.39  4957.8 1731.88    4986 1730.26  4986.5 1729.76
  4999.4 1730.26  5017.4 1731.33  5030.7 1736.63  5180.6 1744.78  5511.8 1751.06
  5550.5 1757.41  5590.7  1773.4  5689.3 1816.44  5744.6 1831.55  5850.8 1870.46
#Mann= 10 ,-1 , 0
  3895.7      .1       0  3907.9     .07       0  4193.2      .1       0
  4365.7     .07       0  4392.1    .035       0    4944     .07       0
    4986     .05       0  4999.4     .07       0  5180.6    .035       0
  5590.7      .1       0
Bank Sta=4986,4999.4
XS Rating Curve= 0 ,0
Exp/Cntr=0.3,0.1

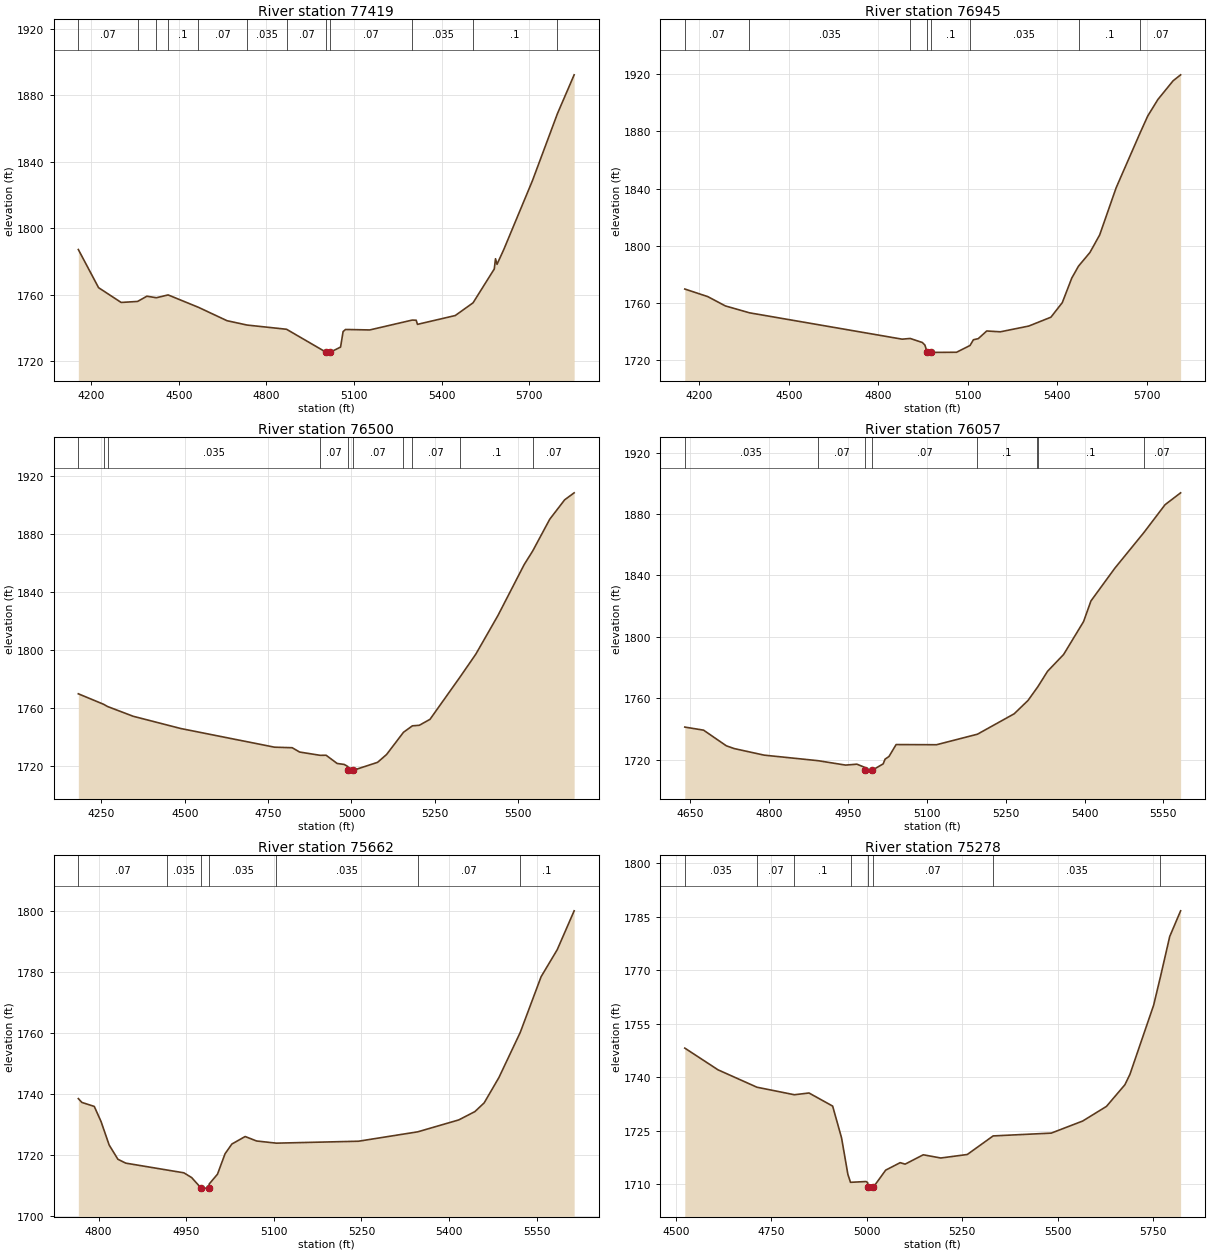
Type RM Length L Ch R = 1 ,77419   ,474,474,474
BEGIN DESCRIPTION:
Cypress Creek 114.0
END DESCRIPTION:
XS GIS Cut Line= 3
      1959625.01     13934425.01        1959025.       13933825.
      1958424.98     13933224.98
#Sta/Elev= 30
  4156.1 1787.15  4225.4  1764.2  4302.7 1755.31  4358.9 1755.92  4390.8 1759.06
  4423.3 1758.15  4463.4 1759.84    4567  1752.4  4664.9 1744.34  4733.6 1741.71
  4868.8 1739.18  5004.4 1725.32  5004.9 1724.82    5018 1725.32  5053.7 1728.47
  5062.3 1737.79  5070.6 1739.05  5153.5 1738.77  5298.9  1744.7  5312.5 1744.62
  5316.9 1742.13  5446.2 1747.44  5507.1 1755.08  5579.8 1775.46    5584 1781.61
  5589.2 1778.25  5612.4 1787.18    5710  1828.4  5795.9 1868.88  5853.2 1892.27
#Mann= 12 ,-1 , 0
  4156.1     .07       0  4358.9      .1       0  4423.3     .07       0
  4463.4      .1       0    4567     .07       0  4733.6    .035       0
  4868.8     .07       0  5004.4     .05       0    5018     .07       0
  5298.9    .035       0  5507.1      .1       0  5795.9     .07       0
Bank Sta=5004.4,5018
XS Rating Curve= 0 ,0
Exp/Cntr=0.3,0.1

Type RM Length L Ch R = 1 ,76945   ,445,445,445
BEGIN DESCRIPTION:
Cypress Creek 113.0
END DESCRIPTION:
XS GIS Cut Line= 3
      1959824.97     13934024.97        1959225.       13933425.
      1958675.02     13932825.02
#Sta/Elev= 30
  4151.5 1769.72  4228.2 1764.44  4287.6 1757.89  4368.3 1753.08  4880.1 1734.64
  4907.3 1735.13    4948  1732.3  4956.5  1730.5  4964.5 1725.37    4965 1724.87
  4978.2 1725.37  5062.6 1725.47  5107.9 1730.23  5119.1 1734.22  5135.4    1735
  5163.8 1740.36  5209.6 1739.79  5304.7 1743.81    5379 1750.01  5417.2 1760.21
    5449  1777.4  5471.5 1785.72  5509.8 1795.28  5542.5 1807.58  5597.7 1840.56
  5677.9 1878.88  5703.8 1890.84  5737.7 1902.33  5788.8 1915.43  5813.9 1919.58
#Mann= 8 ,-1 , 0
  4151.5     .07       0  4368.3    .035       0  4907.3      .1       0
  4964.5     .05       0  4978.2      .1       0  5107.9    .035       0
  5471.5      .1       0  5677.9     .07       0
Bank Sta=4964.5,4978.2
XS Rating Curve= 0 ,0
Exp/Cntr=0.3,0.1

Type RM Length L Ch R = 1 ,76500   ,443,443,443
BEGIN DESCRIPTION:
Cypress Creek 112.0
END DESCRIPTION:
XS GIS Cut Line= 3
        1960075.       13933625.        1959475.       13933075.
      1959025.01     13932575.01
#Sta/Elev= 30
  4181.1 1769.82  4256.6 1762.61  4268.8 1761.03  4345.6  1754.3  4488.6 1745.82
  4769.4 1732.95  4822.3 1732.58  4844.6  1729.6  4906.4 1727.33    4924 1727.38
  4957.1 1721.71  4978.4 1721.03  4989.2 1719.59  4990.6 1716.92  4991.1 1716.42
  5004.4 1716.92  5078.3 1722.49  5105.2 1727.88    5156 1743.25  5182.7  1747.7
  5203.3 1748.07  5235.4 1752.17    5325 1781.22  5372.8 1797.18  5439.3 1823.92
  5517.9 1859.06  5543.5 1868.48  5594.4 1890.33  5639.2 1903.77  5667.7  1908.6
#Mann= 10 ,-1 , 0
  4181.1      .1       0  4256.6     .07       0  4268.8    .035       0
  4906.4     .07       0  4990.6     .05       0  5004.4     .07       0
    5156    .035       0  5182.7     .07       0    5325      .1       0
  5543.5     .07       0
Bank Sta=4990.6,5004.4
XS Rating Curve= 0 ,0
Exp/Cntr=0.3,0.1

Type RM Length L Ch R = 1 ,76057   ,395,395,395
BEGIN DESCRIPTION:
Cypress Creek 111.0
END DESCRIPTION:
XS GIS Cut Line= 3
      1960025.02     13932925.01        1959725.       13932725.
      1959224.98     13932424.99
#Sta/Elev= 30
  4639.2 1741.18  4674.9 1739.18  4718.2 1728.99  4733.3 1727.17  4790.3  1722.9
  4892.6  1719.3  4945.3 1716.42  4966.9 1717.01  4981.4 1714.98  4981.7 1712.99
  4982.2 1712.49  4995.5 1712.99  5016.8 1717.22  5020.4  1720.3  5027.8 1722.01
  5041.4 1729.79  5118.3 1729.68  5196.2 1736.54  5266.1 1749.83  5292.4 1758.51
  5309.1 1766.49  5311.2 1767.49  5329.6 1777.51  5360.2 1788.47  5398.2 1809.91
  5412.2 1823.33  5457.7 1844.67    5513 1867.89  5553.3 1886.03  5582.9 1893.76
#Mann= 8 ,-1 , 0
  4639.2    .035       0  4892.6     .07       0  4981.7     .05       0
  4995.5     .07       0  5196.2      .1       0  5309.1     .07       0
  5311.2      .1       0    5513     .07       0
Bank Sta=4981.7,4995.5
XS Rating Curve= 0 ,0
Exp/Cntr=0.3,0.1

Type RM Length L Ch R = 1 ,75662   ,384,384,384
BEGIN DESCRIPTION:
Cypress Creek 110.0
END DESCRIPTION:
XS GIS Cut Line= 4
        1960225.       13932675.      1960045.21     13932526.11
      1959879.89     13932410.26      1959474.98       13932325.
#Sta/Elev= 30
  4765.2 1738.48  4771.3 1737.22  4792.5 1735.92  4804.1 1730.97    4818 1723.28
    4833 1718.61  4846.4 1717.35  4916.7 1715.11  4945.9 1714.18  4959.3 1712.62
  4974.7 1709.34  4975.2 1708.84  4988.6 1709.34  4989.4 1710.54  5003.5 1713.73
  5016.4 1720.39  5028.1  1723.6  5050.9 1726.06  5070.5  1724.6  5104.3 1723.89
  5244.9 1724.52  5346.5  1727.6  5416.7  1731.5  5444.3 1734.22  5460.2 1737.08
  5485.5 1745.39  5521.9  1760.1  5557.7 1778.38  5585.3 1787.22  5614.3 1799.95
#Mann= 7 ,-1 , 0
  4765.2     .07       0  4916.7    .035       0  4974.7     .05       0
  4988.6    .035       0  5104.3    .035       0  5346.5     .07       0
  5521.9      .1       0
Bank Sta=4974.7,4988.6
XS Rating Curve= 0 ,0
Exp/Cntr=0.3,0.1

Type RM Length L Ch R = 1 ,75278   ,639,639,639
BEGIN DESCRIPTION:
Cypress Creek 109.0
END DESCRIPTION:
XS GIS Cut Line= 3
      1960693.04     13932620.26      1960321.17      13932318.5
      1959504.97     13932239.64
#Sta/Elev= 30
  4522.9 1748.12  4610.1 1742.02  4711.9 1737.15  4809.9 1735.04  4848.3 1735.53
  4910.2 1731.86  4933.6 1722.93  4950.1 1712.73    4957 1710.48  4997.6  1710.7
  5001.9 1710.42  5002.7 1709.07  5003.2 1708.57  5016.6 1709.07  5049.1 1713.89
  5087.1 1715.99  5100.1 1715.58  5147.6  1718.2  5193.5  1717.3  5262.9 1718.28
  5330.6 1723.49  5482.9 1724.28  5565.3 1727.67  5627.5 1731.77  5675.8 1737.84
    5689 1740.76  5751.1 1760.15    5769 1768.15  5793.3 1779.44  5821.8 1786.62
#Mann= 8 ,-1 , 0
  4522.9    .035       0  4711.9     .07       0  4809.9      .1       0
    4957     .07       0  5002.7     .05       0  5016.6     .07       0
  5330.6    .035       0    5769     .07       0
Bank Sta=5002.7,5016.6
XS Rating Curve= 0 ,0
Exp/Cntr=0.3,0.1

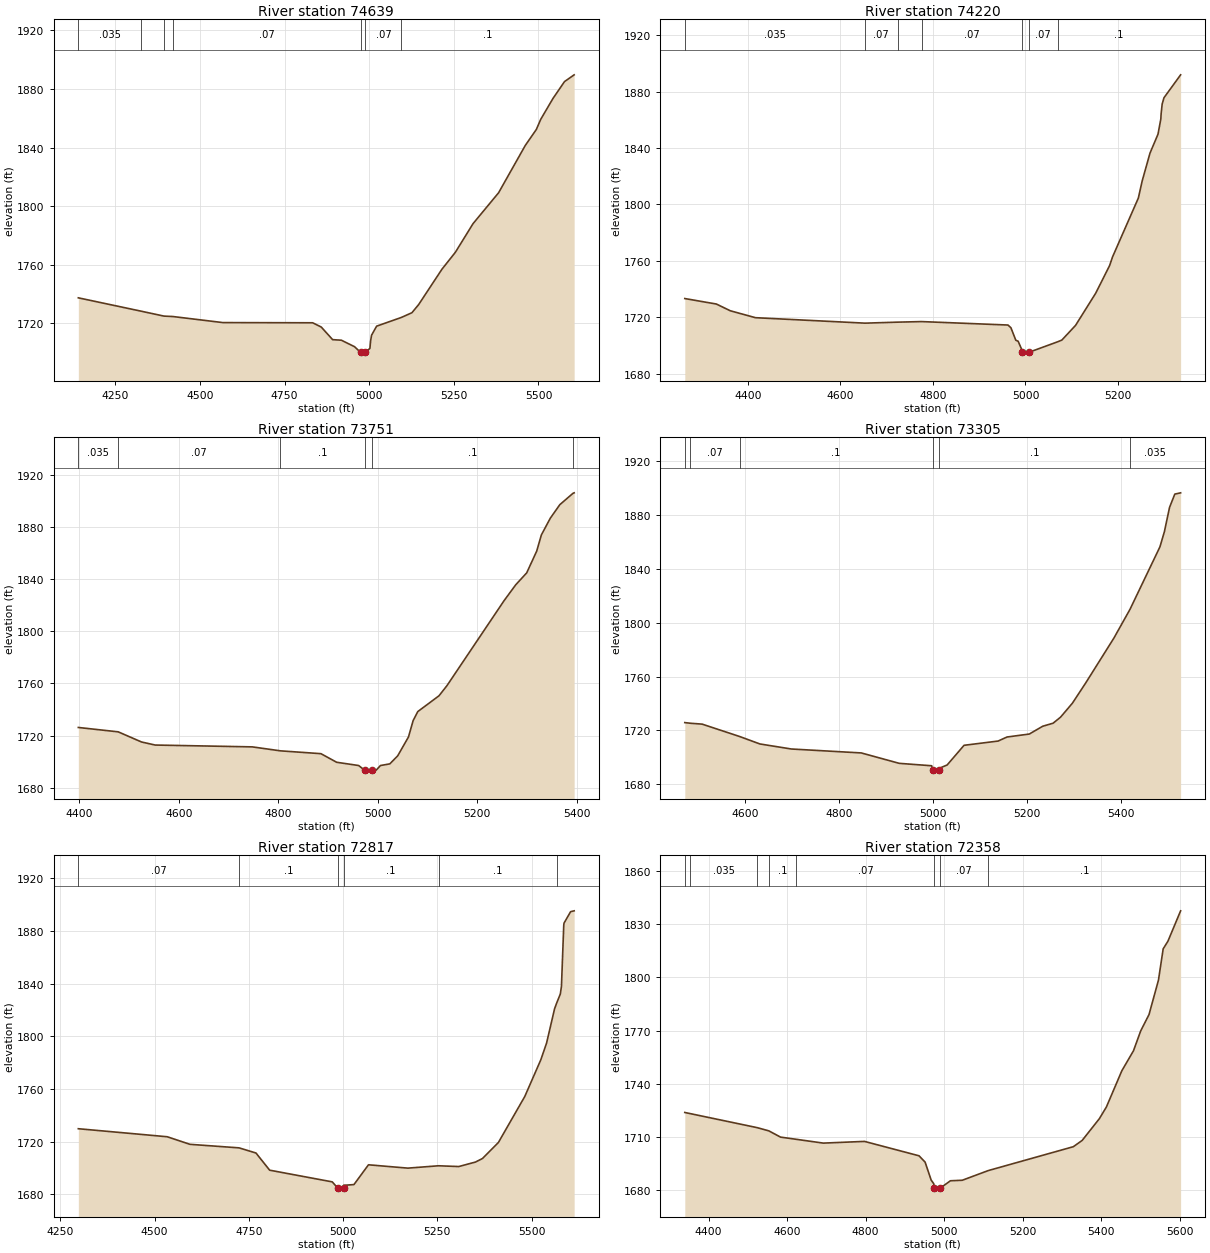
Type RM Length L Ch R = 1 ,74639   ,419,419,419
BEGIN DESCRIPTION:
Cypress Creek 108.0
END DESCRIPTION:
XS GIS Cut Line= 3
      1960889.14     13932253.48      1960160.02     13931759.01
      1959925.01     13931225.02
#Sta/Elev= 30
    4141 1737.42  4325.5 1728.35  4393.8 1724.95  4420.6 1724.64    4568 1720.51
  4833.1 1720.38  4858.5 1717.47    4892 1708.87  4917.9 1708.48  4956.8 1704.05
  4974.6 1700.16  4975.1 1699.66  4988.9 1700.16  5002.2 1702.93  5004.3 1708.15
  5007.1 1711.92    5022 1718.07  5095.1 1724.03  5126.3 1727.26  5146.3 1732.87
    5215 1756.98  5254.5  1768.5  5306.9 1788.12  5382.3 1809.19    5461 1841.47
  5493.7 1852.39  5506.8 1859.37  5542.9 1873.59  5576.9 1885.08  5605.4 1889.71
#Mann= 7 ,-1 , 0
    4141    .035       0  4325.5     .07       0  4393.8    .035       0
  4420.6     .07       0  4974.6     .05       0  4988.9     .07       0
  5095.1      .1       0
Bank Sta=4974.6,4988.9
XS Rating Curve= 0 ,0
Exp/Cntr=0.3,0.1

Type RM Length L Ch R = 1 ,74220   ,469,469,469
BEGIN DESCRIPTION:
Cypress Creek 107.0
END DESCRIPTION:
XS GIS Cut Line= 3
      1960997.82     13931993.86        1960475.       13931475.
        1960325.     13931174.99
#Sta/Elev= 30
  4263.4 1733.35  4331.7 1729.46  4361.8 1724.69  4416.2 1719.79  4652.9 1715.92
  4723.5 1716.63  4775.4 1717.03  4962.1 1714.59  4968.5 1712.68  4979.1  1703.8
  4984.1 1703.12  4991.8 1697.31  4992.4 1695.19  4992.9 1694.69  5006.7 1695.19
  5069.8 1702.75  5078.6 1703.93  5108.2 1714.32  5151.8 1737.13    5182  1756.8
  5188.1 1762.75    5244 1804.52  5252.4 1816.79  5269.2 1836.35  5286.5 1849.78
  5292.7 1860.67  5293.2 1864.08  5295.5 1871.09  5299.4 1875.56  5335.4 1891.81
#Mann= 7 ,-1 , 0
  4263.4    .035       0  4652.9     .07       0  4723.5    .035       0
  4775.4     .07       0  4992.4     .05       0  5006.7     .07       0
  5069.8      .1       0
Bank Sta=4992.4,5006.7
XS Rating Curve= 0 ,0
Exp/Cntr=0.3,0.1

Type RM Length L Ch R = 1 ,73751   ,446,446,446
BEGIN DESCRIPTION:
Cypress Creek 106.0
END DESCRIPTION:
XS GIS Cut Line= 3
      1961103.22     13931713.48        1960825.       13931175.
      1960525.02     13930925.02
#Sta/Elev= 30
  4398.2 1726.26  4478.3 1722.91  4525.2 1715.13  4552.7 1712.79  4747.9 1711.38
  4804.3 1708.35  4885.9 1706.17  4917.4 1699.59  4961.6  1697.1  4974.4  1693.3
  4974.9  1692.8  4988.7  1693.3  4997.2 1693.68  5005.5 1697.09  5024.3 1698.37
  5040.1  1704.5  5061.8 1718.99  5071.1 1731.47  5080.5 1738.43  5123.2 1750.56
  5139.3  1758.4  5253.9 1823.42  5277.3 1835.56  5299.4 1844.73  5319.5 1861.38
  5328.9  1873.8  5346.9 1886.66    5366    1897  5392.4 1905.69  5394.8 1906.08
#Mann= 6 ,-1 , 0
  4398.2    .035       0  4478.3     .07       0  4804.3      .1       0
  4974.4     .05       0  4988.7      .1       0  5392.4    .035       0
Bank Sta=4974.4,4988.7
XS Rating Curve= 0 ,0
Exp/Cntr=0.3,0.1

Type RM Length L Ch R = 1 ,73305   ,488,488,488
BEGIN DESCRIPTION:
Cypress Creek 105.0
END DESCRIPTION:
XS GIS Cut Line= 4
       1961234.7     13931649.15        1961225.       13931125.
       1961225.7       13930992.      1961099.21     13930613.41
#Sta/Elev= 30
  4471.2 1725.74    4483 1725.27  4508.1 1724.61    4588 1715.41  4631.2 1709.87
    4698 1706.13  4847.2  1703.2  4928.2 1695.46  4997.2 1693.67  4999.3 1690.18
  4999.8 1689.68  5013.7 1690.18    5015 1692.05  5030.1 1694.23  5066.2 1708.87
  5138.8 1712.03  5157.7 1715.03  5205.2 1717.24  5233.8 1723.04  5255.8 1725.28
  5271.6 1729.72  5296.9  1740.1  5325.4 1755.22  5385.5 1788.59  5419.8 1809.96
  5483.5 1856.33    5493 1867.59    5504 1885.67  5515.2 1895.54  5527.6  1896.5
#Mann= 6 ,-1 , 0
  4471.2    .035       0    4483     .07       0    4588      .1       0
  4999.3     .05       0  5013.7      .1       0  5419.8    .035       0
Bank Sta=4999.3,5013.7
XS Rating Curve= 0 ,0
Exp/Cntr=0.3,0.1

Type RM Length L Ch R = 1 ,72817   ,459,459,459
BEGIN DESCRIPTION:
Cypress Creek 104.0
END DESCRIPTION:
XS GIS Cut Line= 3
      1961594.63     13931927.42        1961675.       13931225.
        1961775.     13930624.98
#Sta/Elev= 30
  4297.8 1729.77  4533.5 1723.68  4593.9 1717.92  4724.3 1715.23  4769.1 1711.31
  4805.3 1698.28  4971.4 1689.39  4986.8 1684.38  4987.3 1683.88  5001.3 1684.38
  5001.6 1686.78  5028.9 1687.32  5067.5 1702.37  5171.9 1699.83  5253.3 1701.62
  5307.1 1701.04  5351.3 1704.46  5369.9 1707.14  5412.1  1719.3  5482.1 1754.25
  5524.7 1782.17  5539.9 1794.83  5561.2 1820.95  5566.8 1825.31  5576.4  1832.1
  5579.4 1837.94  5585.5 1884.26  5586.2 1885.98  5603.7 1894.67  5613.1 1895.33
#Mann= 6 ,-1 , 0
  4297.8     .07       0  4724.3      .1       0  4986.8     .05       0
  5001.3      .1       0  5253.3      .1       0  5566.8    .035       0
Bank Sta=4986.8,5001.3
XS Rating Curve= 0 ,0
Exp/Cntr=0.3,0.1

Type RM Length L Ch R = 1 ,72358   ,464,464,464
BEGIN DESCRIPTION:
Cypress Creek 103.0
END DESCRIPTION:
XS GIS Cut Line= 3
      1961920.43     13931967.08        1962075.       13931325.
        1962025.       13930725.
#Sta/Elev= 30
  4339.5 1723.81  4352.8  1723.2  4524.1 1715.24  4553.6 1713.43  4583.3 1709.91
  4623.5 1708.67  4692.2 1706.53  4797.1 1707.49  4935.9 1699.37  4951.4  1695.8
  4966.8 1685.67  4973.4 1683.63    4975 1681.06  4975.5 1680.56  4989.5 1681.06
  5015.8 1685.27  5045.9 1685.56  5112.3 1691.03  5328.8  1704.5  5351.4 1708.06
  5395.1 1720.32  5413.1 1726.96  5452.3 1747.34    5482 1758.66  5500.4 1769.88
  5521.5 1779.06  5545.6 1798.53  5557.6 1816.17  5569.7 1820.47    5602 1837.61
#Mann= 8 ,-1 , 0
  4339.5     .07       0  4352.8    .035       0  4524.1     .07       0
  4553.6      .1       0  4623.5     .07       0    4975     .05       0
  4989.5     .07       0  5112.3      .1       0
Bank Sta=4975,4989.5
XS Rating Curve= 0 ,0
Exp/Cntr=0.3,0.1

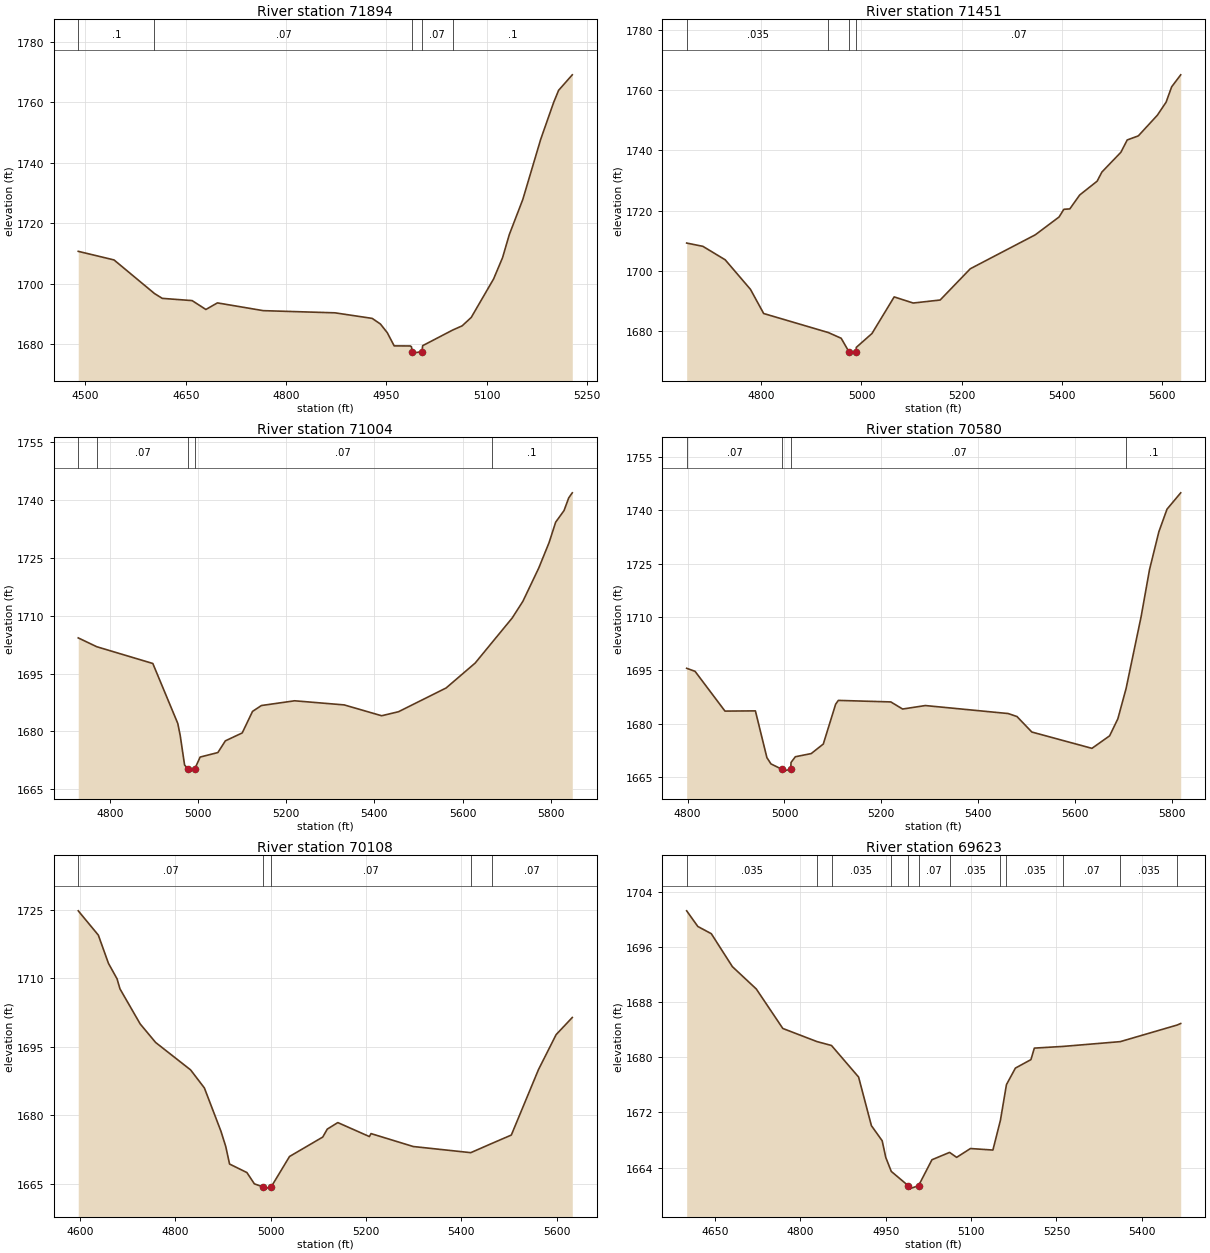
Type RM Length L Ch R = 1 ,71894   ,443,443,443
BEGIN DESCRIPTION:
Cypress Creek 102.0
END DESCRIPTION:
XS GIS Cut Line= 3
      1962274.99     13931725.01        1962525.       13931275.
        1962625.       13931075.
#Sta/Elev= 30
  4489.3 1710.67  4542.8 1707.82  4603.2  1696.7  4614.9 1695.09  4659.5 1694.35
  4680.1 1691.41  4697.3 1693.59  4765.9 1691.02    4873  1690.3  4928.6 1688.46
  4940.9  1686.6  4951.2 1683.72  4961.5 1679.35  4985.5 1679.32  4987.3 1679.07
  4988.6 1677.45  4989.1 1676.95  5003.1 1677.45  5004.1 1679.42  5048.8 1684.58
  5063.1 1685.99  5076.7 1688.78  5110.1 1701.53  5123.5 1708.58  5133.5 1716.18
  5153.7 1727.82  5180.5 1747.78  5199.9 1760.03  5207.3 1764.02  5227.7 1769.14
#Mann= 5 ,-1 , 0
  4489.3      .1       0  4603.2     .07       0  4988.6     .05       0
  5003.1     .07       0  5048.8      .1       0
Bank Sta=4988.6,5003.1
XS Rating Curve= 0 ,0
Exp/Cntr=0.3,0.1

Type RM Length L Ch R = 1 ,71451   ,447,447,447
BEGIN DESCRIPTION:
Cypress Creek 101.0
END DESCRIPTION:
XS GIS Cut Line= 3
      1962444.09     13931838.75        1962725.       13931625.
      1962924.99     13931025.04
#Sta/Elev= 30
  4651.4 1709.23  4683.7 1708.14  4728.2 1703.68  4778.6 1693.88    4805 1685.85
  4933.9 1679.54  4959.6 1677.64  4974.9 1673.21  4975.4 1672.71  4989.5 1673.21
  4989.7 1674.62    5021 1679.22  5065.3 1691.36  5103.2 1689.33    5157 1690.33
  5217.1  1700.7  5346.7 1711.96  5394.2 1717.88  5403.7 1720.43  5415.6 1720.56
  5435.3 1725.17  5470.1 1729.76  5479.6 1732.79  5517.5 1739.35  5530.1 1743.43
  5552.3 1744.79  5590.2 1751.64  5607.7 1755.98  5618.7 1761.05  5636.8 1765.04
#Mann= 4 ,-1 , 0
  4651.4    .035       0  4933.9     .07       0  4974.9     .05       0
  4989.5     .07       0
Bank Sta=4974.9,4989.5
XS Rating Curve= 0 ,0
Exp/Cntr=0.3,0.1

Type RM Length L Ch R = 1 ,71004   ,424,424,424
BEGIN DESCRIPTION:
Cypress Creek 100.0
END DESCRIPTION:
XS GIS Cut Line= 3
      1962611.04     13932089.26        1962875.       13932025.
        1963475.       13931425.
#Sta/Elev= 30
  4728.6 1704.24  4770.5 1701.95  4897.7  1697.6  4954.3 1682.04  4959.8 1678.93
  4969.7 1671.27  4977.9 1670.17  4978.4 1669.67  4992.5 1670.17    5005 1673.32
  5045.2 1674.49  5062.2 1677.53  5100.4 1679.58  5123.8 1685.17  5143.9 1686.69
  5219.2 1687.92  5331.7 1686.85  5416.5 1684.04  5454.7 1685.08  5562.8 1691.25
  5628.6 1697.71  5665.8  1702.9  5712.4 1709.38  5736.8 1713.73  5772.9  1722.4
  5796.2 1728.97  5811.1 1734.26  5830.1 1737.28  5840.8 1740.59  5848.8 1741.88
#Mann= 5 ,-1 , 0
  4728.6    .035       0  4770.5     .07       0  4977.9     .05       0
  4992.5     .07       0  5665.8      .1       0
Bank Sta=4977.9,4992.5
XS Rating Curve= 0 ,0
Exp/Cntr=0.3,0.1

Type RM Length L Ch R = 1 ,70580   ,472,472,472
BEGIN DESCRIPTION:
Cypress Creek 99.0
END DESCRIPTION:
XS GIS Cut Line= 3
      1963125.01     13932474.97        1963175.       13932275.
      1963725.03     13931674.97
#Sta/Elev= 30
  4798.1  1695.6  4815.4 1694.75  4877.2 1683.56    4940 1683.62  4963.8 1670.45
  4972.2  1668.7  4995.1 1667.17  4995.6 1666.67  5012.9 1667.17  5013.6 1669.11
  5022.5 1670.72  5055.3 1671.61  5080.2 1674.29  5105.7  1685.5  5111.3 1686.57
  5219.6 1686.14    5244 1684.14  5290.9 1685.12    5462 1682.87  5480.1 1682.03
  5510.8 1677.67  5634.9 1673.08  5671.4  1676.6  5688.4 1681.39  5705.4 1689.91
  5736.5 1710.17  5753.8 1723.37  5773.1 1734.02  5789.9 1740.37  5818.2 1744.97
#Mann= 4 ,-1 , 0
  4798.1     .07       0  4995.1     .05       0  5012.9     .07       0
  5705.4      .1       0
Bank Sta=4995.1,5012.9
XS Rating Curve= 0 ,0
Exp/Cntr=0.3,0.1

Type RM Length L Ch R = 1 ,70108   ,485,485,485
BEGIN DESCRIPTION:
Cypress Creek 98.0
END DESCRIPTION:
XS GIS Cut Line= 3
        1963525.     13932875.01        1963575.       13932475.
      1963775.01     13931874.98
#Sta/Elev= 30
  4596.9 1724.72    4639 1719.41  4660.2 1713.24  4678.3 1709.83  4684.4 1707.64
  4726.7 1699.98  4759.1 1695.92  4832.5 1689.91  4861.3 1685.97    4896 1676.51
  4906.1 1673.16  4914.1 1669.32  4950.4 1667.46  4966.1 1664.99  4983.6 1664.33
  4984.1 1663.83  5001.4 1664.33  5039.8 1670.97  5109.4 1675.22  5118.9 1676.96
    5141 1678.39  5207.2 1675.33  5210.6 1675.98  5299.2 1673.15  5419.7 1671.81
  5464.2 1673.84  5504.7 1675.66  5561.6 1689.97  5598.6 1697.63  5632.5 1701.38
#Mann= 5 ,-1 , 0
  4596.9     .07       0  4983.6     .05       0  5001.4     .07       0
  5419.7    .035       0  5464.2     .07       0
Bank Sta=4983.6,5001.4
XS Rating Curve= 0 ,0
Exp/Cntr=0.3,0.1

Type RM Length L Ch R = 1 ,69623   ,468,468,468
BEGIN DESCRIPTION:
Cypress Creek 97.0
END DESCRIPTION:
XS GIS Cut Line= 3
      1964166.82     13932848.59        1964025.       13932475.
      1963955.15     13932012.04
#Sta/Elev= 30
  4600.4 1701.26    4620 1698.99  4643.7 1697.94  4680.7 1693.16  4722.7 1689.92
  4769.3 1684.19  4829.2 1682.29  4854.8 1681.72  4902.4 1677.14  4924.9 1670.09
  4943.8  1667.9  4950.2 1665.46  4959.8 1663.45  4989.6 1661.38  4990.1 1660.88
  5007.7 1661.38  5031.2 1665.14  5062.2 1666.21  5074.6 1665.49  5098.9 1666.77
  5138.3 1666.55  5151.5 1670.86  5162.1 1676.04  5177.8 1678.44  5205.1 1679.67
  5211.1 1681.34  5262.1 1681.59    5362 1682.28    5462 1684.69  5468.2 1684.91
#Mann= 12 ,-1 , 0
  4600.4    .035       0  4829.2     .07       0  4854.8    .035       0
  4959.8     .07       0  4989.6     .05       0  5007.7     .07       0
  5062.2    .035       0  5151.5     .07       0  5162.1    .035       0
  5262.1     .07       0    5362    .035       0    5462     .07       0
Bank Sta=4989.6,5007.7
XS Rating Curve= 0 ,0
Exp/Cntr=0.3,0.1

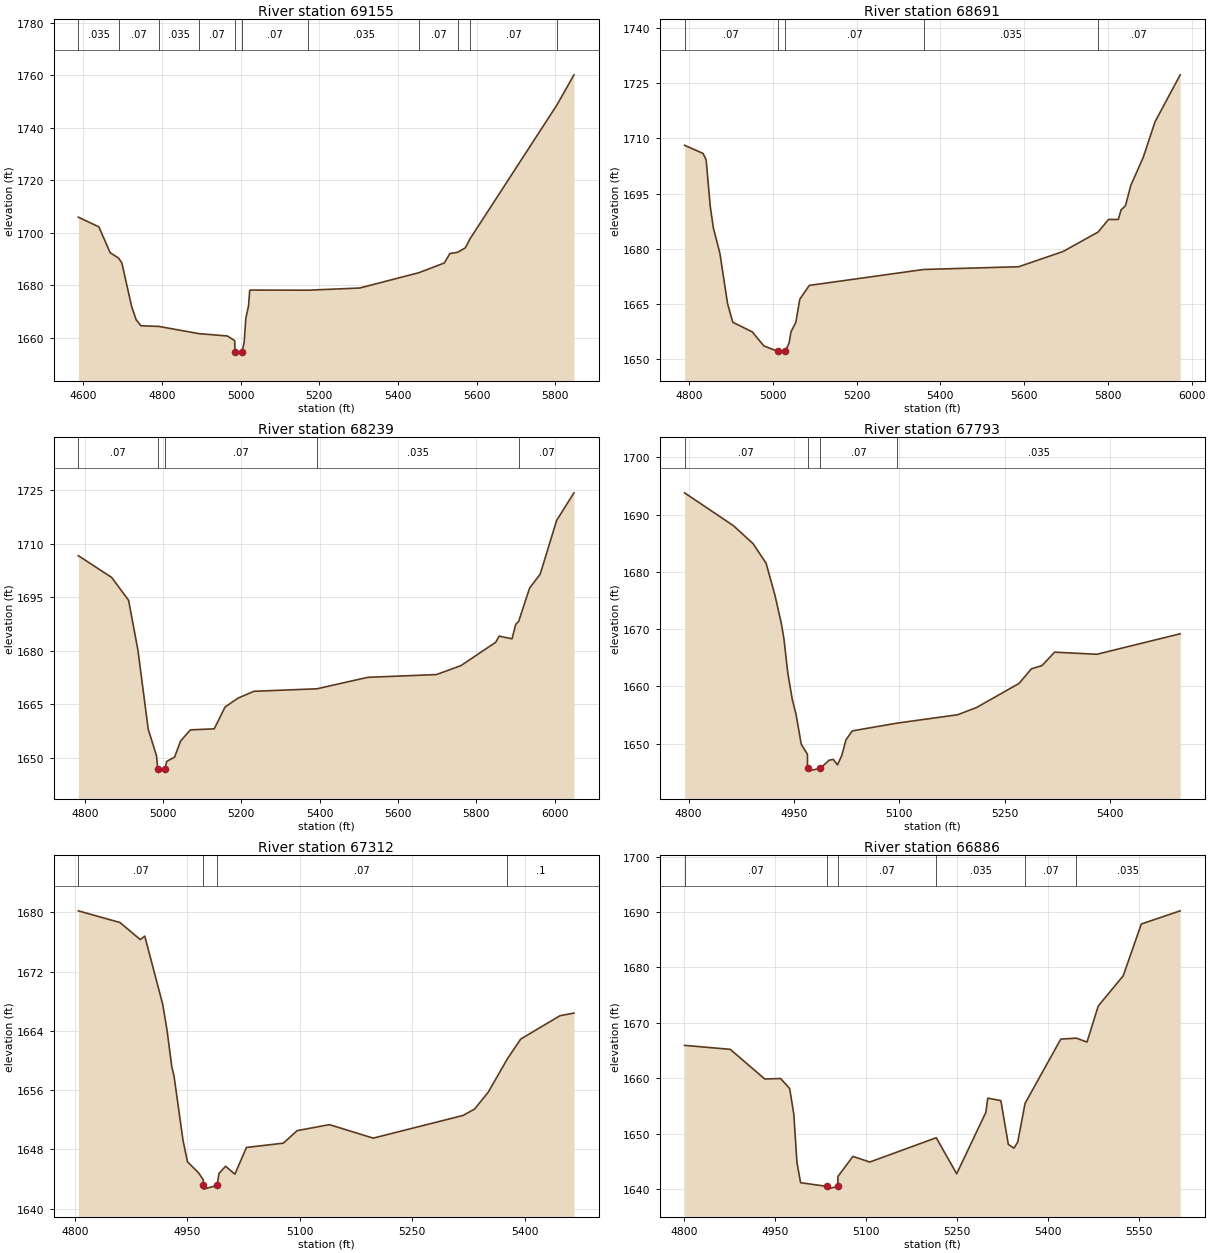
Type RM Length L Ch R = 1 ,69155   ,464,464,464
BEGIN DESCRIPTION:
Cypress Creek 96.0
END DESCRIPTION:
XS GIS Cut Line= 3
      1964474.99     13932624.96        1964375.       13932225.
      1963774.99     13931624.99
#Sta/Elev= 30
  4587.1 1705.98  4639.3 1702.31  4668.2 1692.43  4689.6 1690.41  4697.9 1688.52
  4722.7 1671.99  4734.2 1666.93  4746.6 1664.64  4791.7 1664.39  4893.9 1661.64
  4966.2 1660.75  4984.9 1658.97  4985.7 1654.72  4986.2 1654.22  5003.8 1654.72
    5009 1658.39  5013.2 1667.46  5020.1 1672.23    5023 1677.95  5024.4 1678.22
  5172.3 1678.18    5303 1679.01  5453.7 1684.85  5518.1 1688.53  5532.1 1692.11
  5552.3 1692.62  5571.7 1694.32  5583.1 1697.63  5804.9 1748.77  5847.9 1760.17
#Mann= 11 ,-1 , 0
  4587.1    .035       0  4689.6     .07       0  4791.7    .035       0
  4893.9     .07       0  4985.7     .05       0  5003.8     .07       0
  5172.3    .035       0  5453.7     .07       0  5552.3    .035       0
  5583.1     .07       0  5804.9      .1       0
Bank Sta=4985.7,5003.8
XS Rating Curve= 0 ,0
Exp/Cntr=0.3,0.1

Type RM Length L Ch R = 1 ,68691   ,452,452,452
BEGIN DESCRIPTION:
Cypress Creek 95.0
END DESCRIPTION:
XS GIS Cut Line= 3
      1964874.99     13932374.96        1964825.       13932175.
      1964093.37     13931526.63
#Sta/Elev= 30
    4789 1708.15  4833.1 1705.93  4840.5  1704.2  4850.4 1691.51  4857.8  1685.7
  4873.3 1678.83  4891.8 1665.08  4904.2 1660.06  4950.6 1657.46  4978.4 1653.64
  5011.3 1652.18  5011.8 1651.68  5029.5 1652.18  5038.6 1654.42    5043 1657.42
  5054.8 1660.07  5064.2 1666.33  5086.9 1670.08  5360.3 1674.41  5586.9 1675.15
  5693.2  1679.3  5776.6 1684.58  5801.6    1688    5825 1687.99  5831.3 1690.55
    5842 1691.73  5854.7 1697.24  5884.4 1704.86  5912.6 1714.53  5972.7 1727.29
#Mann= 5 ,-1 , 0
    4789     .07       0  5011.3     .05       0  5029.5     .07       0
  5360.3    .035       0  5776.6     .07       0
Bank Sta=5011.3,5029.5
XS Rating Curve= 0 ,0
Exp/Cntr=0.3,0.1

Type RM Length L Ch R = 1 ,68239   ,446,446,446
BEGIN DESCRIPTION:
Cypress Creek 94.0
END DESCRIPTION:
XS GIS Cut Line= 3
      1965275.03     13932075.03        1965125.       13931925.
      1964190.89     13931436.94
#Sta/Elev= 30
  4783.5 1706.67  4868.7 1700.56  4911.9 1694.16  4935.8 1680.19    4962 1658.08
  4983.3 1650.58  4986.6 1646.79  4987.1 1646.29  5004.8 1646.79  5009.3 1649.02
  5029.4 1650.22  5044.9 1654.75  5069.8 1657.85  5130.7 1658.14  5158.3 1664.25
  5191.6 1666.76  5232.2 1668.66    5393 1669.36  5522.9 1672.57  5698.5 1673.35
  5760.8 1675.85  5849.7 1682.39  5858.6 1684.12  5891.4 1683.37  5900.9 1687.41
  5908.4 1688.26  5936.3 1697.58  5963.4  1701.5  6005.3 1716.52  6049.6 1724.27
#Mann= 5 ,-1 , 0
  4783.5     .07       0  4986.6     .05       0  5004.8     .07       0
    5393    .035       0  5908.4     .07       0
Bank Sta=4986.6,5004.8
XS Rating Curve= 0 ,0
Exp/Cntr=0.3,0.1

Type RM Length L Ch R = 1 ,67793   ,481,481,481
BEGIN DESCRIPTION:
Cypress Creek 93.0
END DESCRIPTION:
XS GIS Cut Line= 3
      1965474.99       13931575.        1965275.       13931525.
      1964775.67     13931530.43
#Sta/Elev= 30
  4794.2 1693.79  4863.9 1688.04  4891.8  1684.9  4910.3 1681.48  4923.2 1675.74
    4932 1670.93  4935.6 1668.34  4941.2 1662.28  4947.4 1657.78  4952.9 1655.08
  4960.3 1649.87  4969.1 1648.12  4969.2 1645.68  4969.7 1645.18  4987.5 1645.68
    5000 1647.09  5005.9 1647.23  5011.9 1646.27    5018 1647.93    5024 1650.67
    5033 1652.21  5096.5 1653.56    5183 1655.03    5210  1656.3  5270.3  1660.5
  5287.9 1663.05    5303 1663.62    5321 1665.96    5381 1665.59  5499.7 1669.17
#Mann= 4 ,-1 , 0
  4794.2     .07       0  4969.2     .05       0  4987.5     .07       0
  5096.5    .035       0
Bank Sta=4969.2,4987.5
XS Rating Curve= 0 ,0
Exp/Cntr=0.3,0.1

Type RM Length L Ch R = 1 ,67312   ,426,426,426
BEGIN DESCRIPTION:
Cypress Creek 92.0
END DESCRIPTION:
XS GIS Cut Line= 3
      1965474.96       13931075.        1965275.       13931075.
      1964825.03     13931174.99
#Sta/Elev= 30
  4804.7 1680.19  4860.3 1678.61  4887.3 1676.31  4893.3 1676.78  4917.3 1667.56
  4923.1 1664.01  4929.3 1659.18  4932.3 1657.92  4944.3 1649.23  4950.3 1646.34
  4965.3 1644.82  4971.3 1643.91  4971.4 1643.15  4971.9 1642.65  4989.7 1643.15
  4992.3 1644.77  5001.1 1645.74  5013.5 1644.67  5028.9 1648.27  5078.1 1648.85
  5096.5 1650.54  5139.5 1651.35  5197.9 1649.53  5317.8 1652.59  5333.2 1653.46
  5351.6 1655.77  5376.6 1660.19  5394.6 1662.89  5446.9 1666.04  5465.6  1666.4
#Mann= 4 ,-1 , 0
  4804.7     .07       0  4971.4     .05       0  4989.7     .07       0
  5376.6      .1       0
Bank Sta=4971.4,4989.7
XS Rating Curve= 0 ,0
Exp/Cntr=0.3,0.1

Type RM Length L Ch R = 1 ,66886   ,324,324,324
BEGIN DESCRIPTION:
Cypress Creek 91.0
END DESCRIPTION:
XS GIS Cut Line= 3
      1965274.96       13930725.        1965075.       13930725.
      1964475.03     13930874.99
#Sta/Elev= 30
  4800.4 1665.92  4875.8  1665.2  4932.8 1659.85    4959 1659.93    4974 1658.11
  4980.8 1653.47    4986 1644.74    4992 1641.12  5035.1 1640.46  5035.6 1639.96
  5053.5 1640.46  5053.6 1642.24  5078.4 1645.87  5106.2 1644.85    5216 1649.24
  5249.7 1642.73  5297.9 1653.82    5301 1656.39  5322.7 1655.94    5335 1648.05
  5344.3 1647.36  5350.5 1648.45  5362.6 1655.43  5421.6 1667.05  5447.5 1667.22
  5464.9 1666.51  5483.5 1673.03  5524.7 1678.48  5554.6 1687.83  5618.8 1690.21
#Mann= 6 ,-1 , 0
  4800.4     .07       0  5035.1     .05       0  5053.5     .07       0
    5216    .035       0  5362.6     .07       0  5447.5    .035       0
Bank Sta=5035.1,5053.5
XS Rating Curve= 0 ,0
Exp/Cntr=0.3,0.1