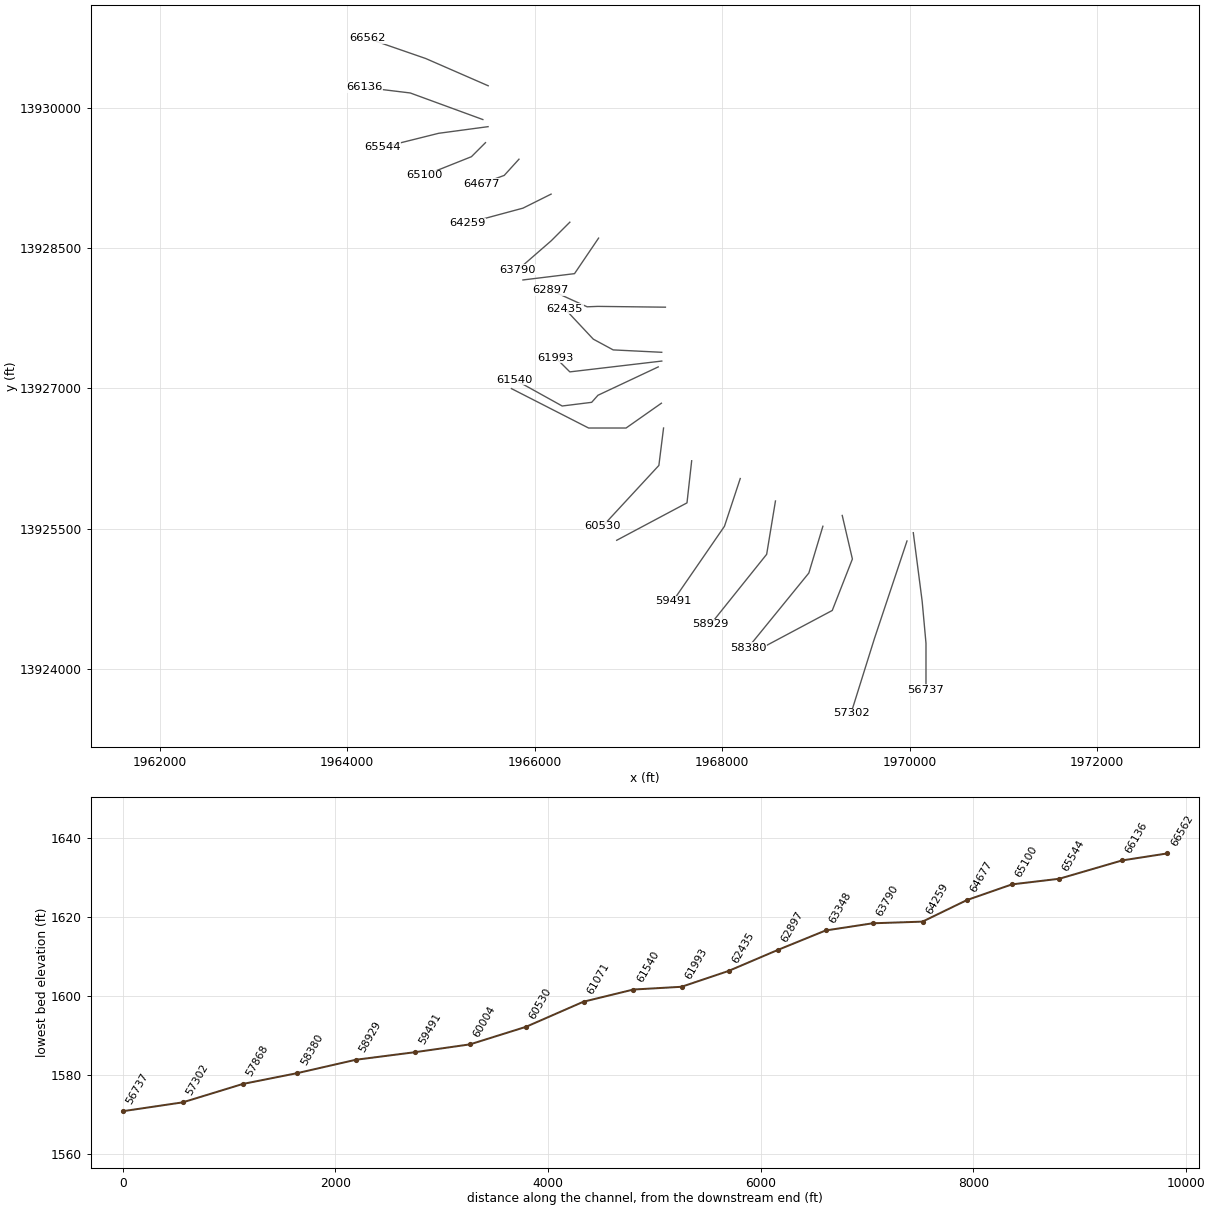
HEC-RAS study Cypress Creek.prj: Cypress Creek Base Level Engineering

--- Cypress Creek.g01 (geometry) --- (continued)

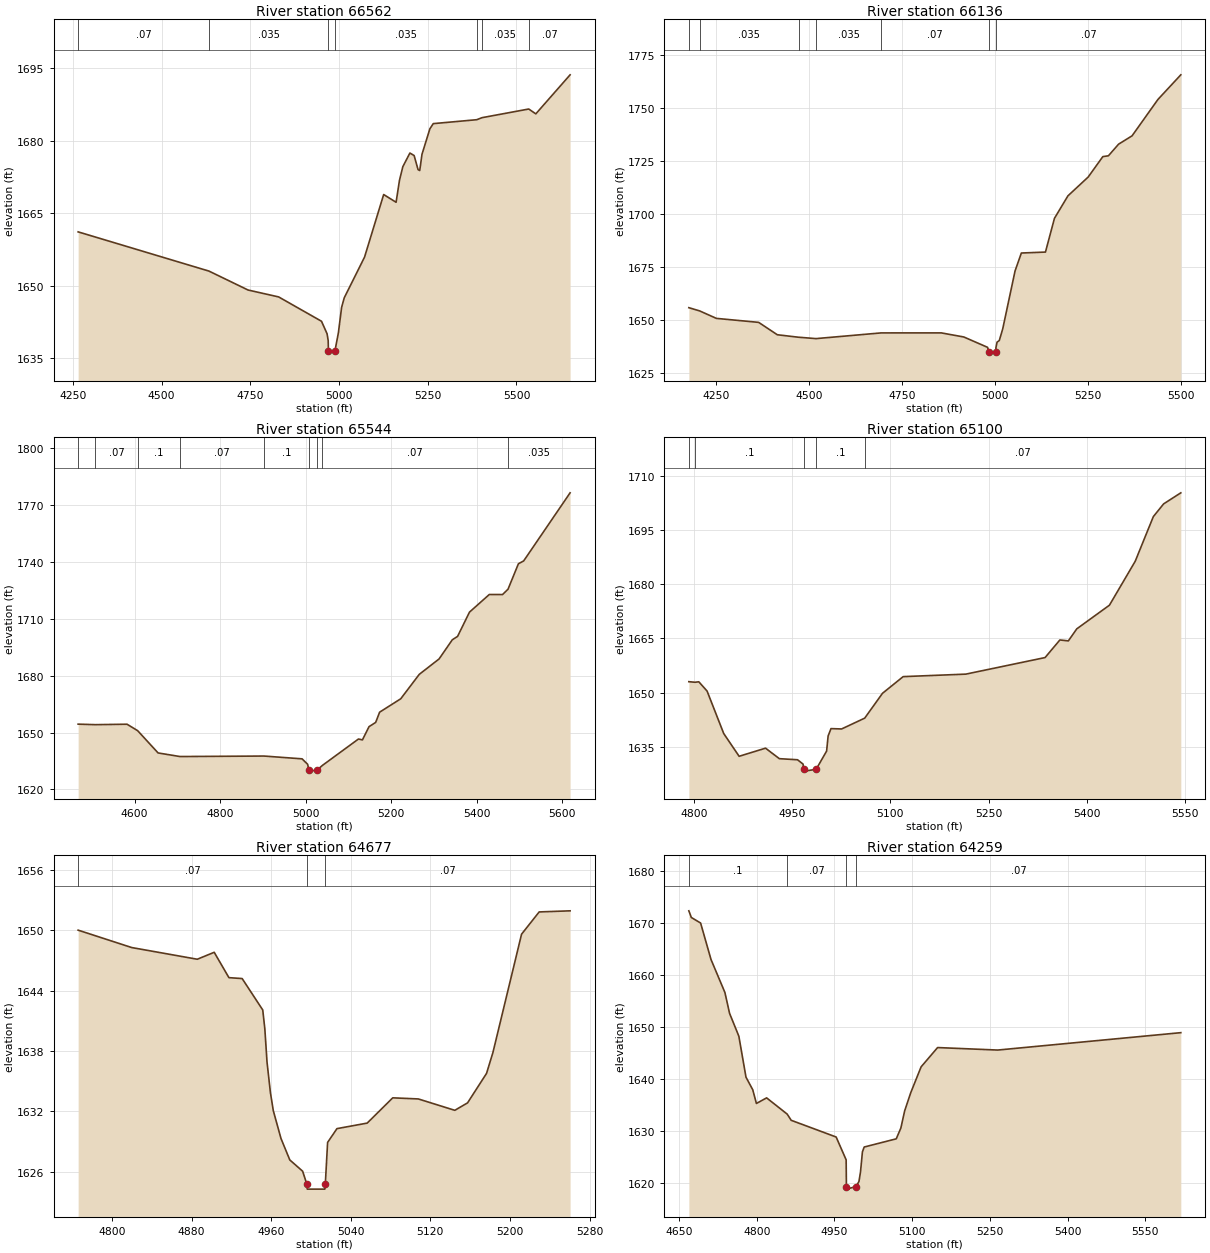
Type RM Length L Ch R = 1 ,66562   ,426,426,426
BEGIN DESCRIPTION:
Cypress Creek 90.0
END DESCRIPTION:
XS GIS Cut Line= 3
      1965504.01     13930232.96      1964836.82     13930524.53
      1964215.03     13930740.04
#Sta/Elev= 30
  4264.9 1661.17  4633.6 1653.06  4743.6 1649.15  4829.9 1647.72  4950.6 1642.69
  4966.3 1640.11  4969.5 1638.67  4970.1  1636.6  4970.6  1636.1  4988.6  1636.6
  4998.2  1640.3  5007.3 1645.56  5014.7 1647.54  5071.9 1655.95  5125.8 1668.89
  5160.8 1667.29  5170.3 1671.82  5179.8 1674.65  5199.7 1677.47  5211.6 1676.95
  5222.7 1674.04  5227.4 1673.85  5233.8 1677.22    5256 1682.48  5265.5 1683.55
    5388 1684.36  5402.9 1684.78  5534.5 1686.57  5554.5 1685.57  5651.1 1693.64
#Mann= 7 ,-1 , 0
  4264.9     .07       0  4633.6    .035       0  4970.1    .035       0
  4988.6    .035       0    5388     .07       0  5402.9    .035       0
  5534.5     .07       0
Bank Sta=4970.1,4988.6
XS Rating Curve= 0 ,0
Exp/Cntr=0.3,0.1

Type RM Length L Ch R = 1 ,66136   ,592,592,592
BEGIN DESCRIPTION:
Cypress Creek 89.0
END DESCRIPTION:
XS GIS Cut Line= 3
      1965446.79     13929872.02      1964672.13     13930156.15
       1964179.4     13930216.22
#Sta/Elev= 30
    4178 1655.76    4207 1654.24    4252 1650.71  4365.5 1648.83  4415.6 1642.99
  4472.6 1641.82  4519.8 1641.17  4694.6 1643.86  4855.9 1643.87  4916.6 1641.94
  4980.5 1637.05    4984 1634.82  4984.5 1634.32  5002.6 1634.82  5002.9  1636.9
  5005.9 1639.49  5011.9 1640.27  5021.1 1645.75  5054.3 1673.12  5071.2 1681.55
  5135.9 1681.99  5160.1 1697.92  5196.3 1708.52  5250.7  1717.4    5290 1727.02
  5305.1 1727.42  5332.3 1732.89  5368.6 1736.84  5438.1    1754  5499.5 1765.61
#Mann= 7 ,-1 , 0
    4178    .063       0    4207    .035       0  4472.6     .07       0
  4519.8    .035       0  4694.6     .07       0    4984     .05       0
  5002.6     .07       0
Bank Sta=4984,5002.6
XS Rating Curve= 0 ,0
Exp/Cntr=0.3,0.1

Type RM Length L Ch R = 1 ,65544   ,444,444,444
BEGIN DESCRIPTION:
Cypress Creek 88.0
END DESCRIPTION:
XS GIS Cut Line= 3
      1965502.67       13929796.        1964975.       13929725.
      1964374.99       13929575.
#Sta/Elev= 30
  4467.9 1654.41    4508 1654.14  4582.3 1654.37  4607.1 1650.98  4654.9 1639.25
  4706.1 1637.35  4902.7 1637.61  4991.8 1636.14  5004.8 1633.26  5007.9 1630.17
  5008.4 1629.67  5026.5 1630.17  5039.4 1632.69  5123.7 1646.58    5133 1646.12
  5148.4 1653.09  5163.9 1655.31  5173.2 1660.71  5222.6 1667.77  5265.9 1680.62
  5312.3 1688.75  5343.2 1698.83  5355.6 1700.63  5383.4 1713.39  5429.8 1722.69
  5460.7 1722.65  5473.6 1725.48  5497.9 1738.87  5510.2 1740.37  5618.8 1776.22
#Mann= 9 ,-1 , 0
  4467.9    .035       0    4508     .07       0  4607.1      .1       0
  4706.1     .07       0  4902.7      .1       0  5007.9     .05       0
  5026.5      .1       0  5039.4     .07       0  5473.6    .035       0
Bank Sta=5007.9,5026.5
XS Rating Curve= 0 ,0
Exp/Cntr=0.3,0.1

Type RM Length L Ch R = 1 ,65100   ,423,423,423
BEGIN DESCRIPTION:
Cypress Creek 87.0
END DESCRIPTION:
XS GIS Cut Line= 3
      1965474.98     13929624.98        1965325.       13929475.
      1964825.02     13929275.01
#Sta/Elev= 30
  4792.5 1653.03  4801.9 1652.87  4807.7    1653  4820.3 1650.44  4845.7 1638.67
  4869.2 1632.36  4909.5 1634.61  4930.6  1631.7  4958.3  1631.4  4966.7 1630.21
  4968.1 1628.75  4968.6 1628.25  4986.7 1628.75  5002.7 1633.81    5005 1637.99
  5009.4 1640.03  5025.6 1639.93  5060.8 1642.93    5088 1649.82  5119.5 1654.43
    5215 1655.12    5336 1659.71  5358.6 1664.59  5371.5 1664.33  5384.4 1667.67
  5434.2 1674.22  5473.5 1686.38  5501.2 1698.77  5516.9 1702.29  5543.1 1705.35
#Mann= 5 ,-1 , 0
  4792.5     .07       0  4801.9      .1       0  4968.1     .05       0
  4986.7      .1       0  5060.8     .07       0
Bank Sta=4968.1,4986.7
XS Rating Curve= 0 ,0
Exp/Cntr=0.3,0.1

Type RM Length L Ch R = 1 ,64677   ,418,418,418
BEGIN DESCRIPTION:
Cypress Creek 86.0
END DESCRIPTION:
XS GIS Cut Line= 3
      1965832.44     13929448.29        1965675.       13929275.
      1965430.51     13929185.17
#Sta/Elev= 30
  4765.9 1650.01  4819.8 1648.28  4885.7 1647.12  4902.7 1647.81  4917.5 1645.29
  4930.8  1645.2  4951.5 1642.08  4953.6  1640.2  4955.8  1636.9  4959.2 1633.88
  4962.1 1632.08  4969.8 1629.32  4978.7 1627.18  4991.6 1626.06  4995.8 1624.78
  4996.3 1624.28  5013.9 1624.28  5014.4 1624.78  5016.7 1628.92  5026.1 1630.29
  5056.5 1630.84  5082.2 1633.35  5107.9 1633.24  5144.6 1632.11  5157.4 1632.85
  5176.5 1635.78  5182.9 1637.85  5211.7 1649.61  5229.4 1651.82  5260.5 1651.93
#Mann= 3 ,-1 , 0
  4765.9     .07       0  4995.8     .05       0  5014.4     .07       0
Bank Sta=4995.8,5014.4
XS Rating Curve= 0 ,0
Exp/Cntr=0.3,0.1

Type RM Length L Ch R = 1 ,64259   ,469,469,469
BEGIN DESCRIPTION:
Cypress Creek 85.0
END DESCRIPTION:
XS GIS Cut Line= 3
        1966175.       13929075.        1965875.       13928925.
      1965282.12     13928764.99
#Sta/Elev= 30
  4668.9 1672.42  4673.7 1671.14  4691.6 1670.07  4711.7 1663.04  4738.5 1656.69
  4747.5 1652.67  4765.4 1648.27  4779.2 1640.37  4792.2 1637.96  4799.3 1635.31
    4819 1636.39  4858.7 1633.26  4866.4 1632.07  4953.2 1628.85  4972.5 1624.45
    4973 1619.31  4973.5 1618.81  4991.6 1619.31  4997.2 1620.28  5000.2 1622.12
  5003.9 1625.98  5007.3 1626.92  5069.2  1628.5  5078.1 1630.58  5085.4 1633.88
  5097.2  1637.4  5117.2 1642.37    5149 1646.08    5265  1645.6  5618.4 1648.95
#Mann= 4 ,-1 , 0
  4668.9      .1       0  4858.7     .07       0    4973     .05       0
  4991.6     .07       0
Bank Sta=4973,4991.6
XS Rating Curve= 0 ,0
Exp/Cntr=0.3,0.1

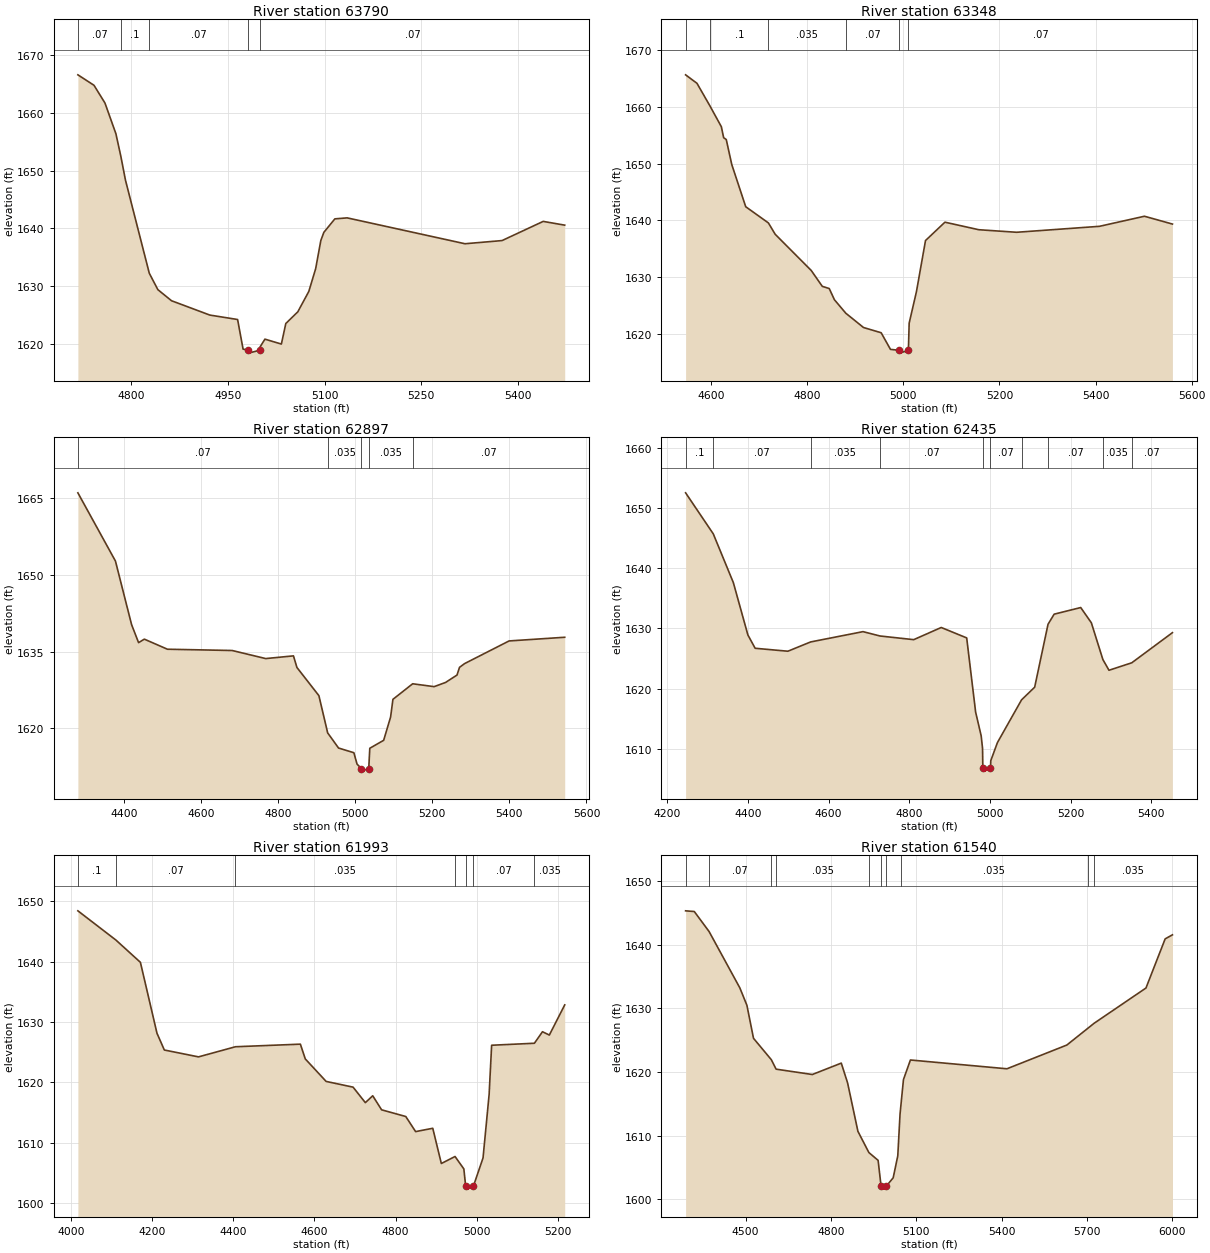
Type RM Length L Ch R = 1 ,63790   ,442,442,442
BEGIN DESCRIPTION:
Cypress Creek 84.0
END DESCRIPTION:
XS GIS Cut Line= 3
      1966374.97     13928774.97        1966175.       13928575.
      1965818.62     13928264.76
#Sta/Elev= 30
  4717.2 1666.58  4742.2 1664.77  4759.2  1661.7  4776.2 1656.38  4783.9 1652.45
    4791 1648.36    4828 1632.22  4841.3 1629.38  4862.5 1627.46  4921.9 1624.98
    4965 1624.21  4973.5 1619.09  4981.1 1618.89  4981.6 1618.39  4999.7 1618.89
    5000 1619.49  5007.4 1620.81  5032.9 1619.96  5039.8 1623.52  5058.4 1625.54
  5075.5 1629.08  5086.1 1633.01  5094.1 1637.88  5098.8  1639.3  5115.9 1641.64
    5135 1641.81  5317.8 1637.33  5375.3 1637.88  5439.1  1641.2  5472.5 1640.55
#Mann= 5 ,-1 , 0
  4717.2     .07       0  4783.9      .1       0    4828     .07       0
  4981.1     .05       0  4999.7     .07       0
Bank Sta=4981.1,4999.7
XS Rating Curve= 0 ,0
Exp/Cntr=0.3,0.1

Type RM Length L Ch R = 1 ,63348   ,451,451,451
BEGIN DESCRIPTION:
Cypress Creek 83.0
END DESCRIPTION:
XS GIS Cut Line= 3
      1966681.69     13928604.83        1966425.       13928225.
      1965874.56     13928157.49
#Sta/Elev= 30
    4547 1665.69  4570.7 1664.19    4598 1660.15  4621.4 1656.53  4626.2 1654.59
  4631.6 1654.27  4643.1 1649.85  4672.1 1642.41  4719.3 1639.55  4733.4 1637.55
  4808.4 1631.16  4831.4 1628.36  4845.9 1627.97  4856.6    1626  4880.4 1623.61
  4917.2 1621.09  4953.9 1620.17  4973.3 1617.23  4991.9 1617.07  4992.4 1616.57
  5010.6 1617.07  5012.2 1621.86  5027.3  1627.4  5046.2 1636.44  5086.6 1639.68
  5157.2 1638.35  5235.8  1637.9  5408.1 1638.95  5501.8 1640.73    5560 1639.35
#Mann= 6 ,-1 , 0
    4547     .07       0    4598      .1       0  4719.3    .035       0
  4880.4     .07       0  4991.9     .05       0  5010.6     .07       0
Bank Sta=4991.9,5010.6
XS Rating Curve= 0 ,0
Exp/Cntr=0.3,0.1

Type RM Length L Ch R = 1 ,62897   ,462,462,462
BEGIN DESCRIPTION:
Cypress Creek 82.0
END DESCRIPTION:
XS GIS Cut Line= 4
      1967394.82     13927866.51        1966675.       13927875.
      1966559.51     13927870.63      1966169.89     13928047.92
#Sta/Elev= 30
  4280.1 1666.07  4377.6 1652.72  4419.5 1640.28  4437.6 1636.76  4452.6 1637.44
  4512.6 1635.47  4680.6 1635.22  4767.6 1633.64  4839.6 1634.17  4848.6  1631.9
  4905.6 1626.39  4928.4  1619.1  4956.6 1616.14  4996.4 1615.22  5004.6    1613
    5016 1612.12  5016.5 1611.62    5035 1612.12  5037.7 1616.09  5073.7 1617.65
  5091.7  1622.2  5097.8 1625.67    5149 1628.71  5204.7 1628.15  5234.4 1628.97
  5264.1 1630.42  5270.6 1631.93  5283.8 1632.66  5399.2 1637.09  5543.6 1637.81
#Mann= 5 ,-1 , 0
  4280.1     .07       0  4928.4    .035       0    5016    .035       0
    5035    .035       0    5149     .07       0
Bank Sta=5016,5035
XS Rating Curve= 0 ,0
Exp/Cntr=0.3,0.1

Type RM Length L Ch R = 1 ,62435   ,442,442,442
BEGIN DESCRIPTION:
Cypress Creek 81.0
END DESCRIPTION:
XS GIS Cut Line= 4
      1967355.55      13927384.3      1966837.37     13927409.96
        1966625.       13927525.      1966320.07      13927851.1
#Sta/Elev= 30
  4245.6  1652.5  4314.2 1645.69    4364 1637.59    4400 1628.91    4418  1626.7
  4499.1 1626.21  4555.5 1627.75  4685.4 1629.46  4727.4 1628.74  4811.1 1628.13
  4879.3 1630.15  4942.4 1628.42  4964.6 1616.09  4978.3 1612.17  4981.7 1610.09
  4982.4 1606.81  4982.9 1606.31  5001.4 1606.81  5002.1 1608.04  5018.6 1611.05
  5078.4 1618.14  5110.9 1620.24    5144 1630.68  5159.2 1632.36  5225.1 1633.46
  5251.4 1630.93    5280 1624.83  5295.1 1623.05  5351.6 1624.29  5452.4 1629.29
#Mann= 10 ,-1 , 0
  4245.6      .1       0  4314.2     .07       0  4555.5    .035       0
  4727.4     .07       0  4982.4     .05       0  5001.4     .07       0
  5078.4    .035       0    5144     .07       0    5280    .035       0
  5351.6     .07       0
Bank Sta=4982.4,5001.4
XS Rating Curve= 0 ,0
Exp/Cntr=0.3,0.1

Type RM Length L Ch R = 1 ,61993   ,453,453,453
BEGIN DESCRIPTION:
Cypress Creek 80.0
END DESCRIPTION:
XS GIS Cut Line= 3
      1967355.99     13927290.67        1966375.       13927175.
      1966225.01     13927324.99
#Sta/Elev= 30
    4017 1648.45  4110.8  1643.6  4171.1 1639.91    4212 1628.14  4230.1 1625.37
  4314.3 1624.23  4405.4 1625.91  4565.4 1626.34  4577.5 1623.89  4628.9 1620.16
  4695.3 1619.21  4725.5 1616.64  4743.7 1617.78  4765.6 1615.45  4825.2 1614.34
  4849.4 1611.84  4891.7 1612.39  4912.8 1606.55  4946.6 1607.71  4968.3 1605.65
  4972.8  1602.8  4973.3  1602.3  4991.9  1602.8  5015.6 1607.48  5030.6 1618.01
  5036.8 1626.16  5142.2 1626.49  5162.1  1628.4    5179 1627.85  5216.9 1632.85
#Mann= 7 ,-1 , 0
    4017      .1       0  4110.8     .07       0  4405.4    .035       0
  4946.6     .07       0  4972.8     .05       0  4991.9     .07       0
  5142.2    .035       0
Bank Sta=4972.8,4991.9
XS Rating Curve= 0 ,0
Exp/Cntr=0.3,0.1

Type RM Length L Ch R = 1 ,61540   ,469,469,469
BEGIN DESCRIPTION:
Cypress Creek 79.0
END DESCRIPTION:
XS GIS Cut Line= 5
      1967318.16     13927228.08        1966675.       13926925.
      1966608.04     13926849.54      1966293.31     13926810.33
      1965785.02      13927092.7
#Sta/Elev= 30
  4289.3 1645.33  4319.9 1645.22  4371.9 1642.07  4479.9 1633.22  4504.7 1630.49
  4527.9  1625.3  4590.6 1621.93  4607.3 1620.45  4734.6 1619.61  4836.3  1621.4
  4858.6 1618.27  4894.7 1610.69  4933.2 1607.35  4965.7 1606.12    4976  1602.1
  4976.5  1601.6  4995.1  1602.1  5018.7 1603.38  5034.8 1606.83  5042.8 1613.42
  5046.7 1615.18  5054.8 1618.82  5079.2 1621.89  5418.3 1620.51  5628.8 1624.24
  5701.4 1626.83  5724.6 1627.66  5906.8  1633.2  5974.2 1640.92  5999.8 1641.56
#Mann= 10 ,-1 , 0
  4289.3      .1       0  4371.9     .07       0  4590.6      .1       0
  4607.3    .035       0  4933.2     .07       0    4976     .05       0
  4995.1     .07       0  5046.7    .035       0  5701.4     .07       0
  5724.6    .035       0
Bank Sta=4976,4995.1
XS Rating Curve= 0 ,0
Exp/Cntr=0.3,0.1

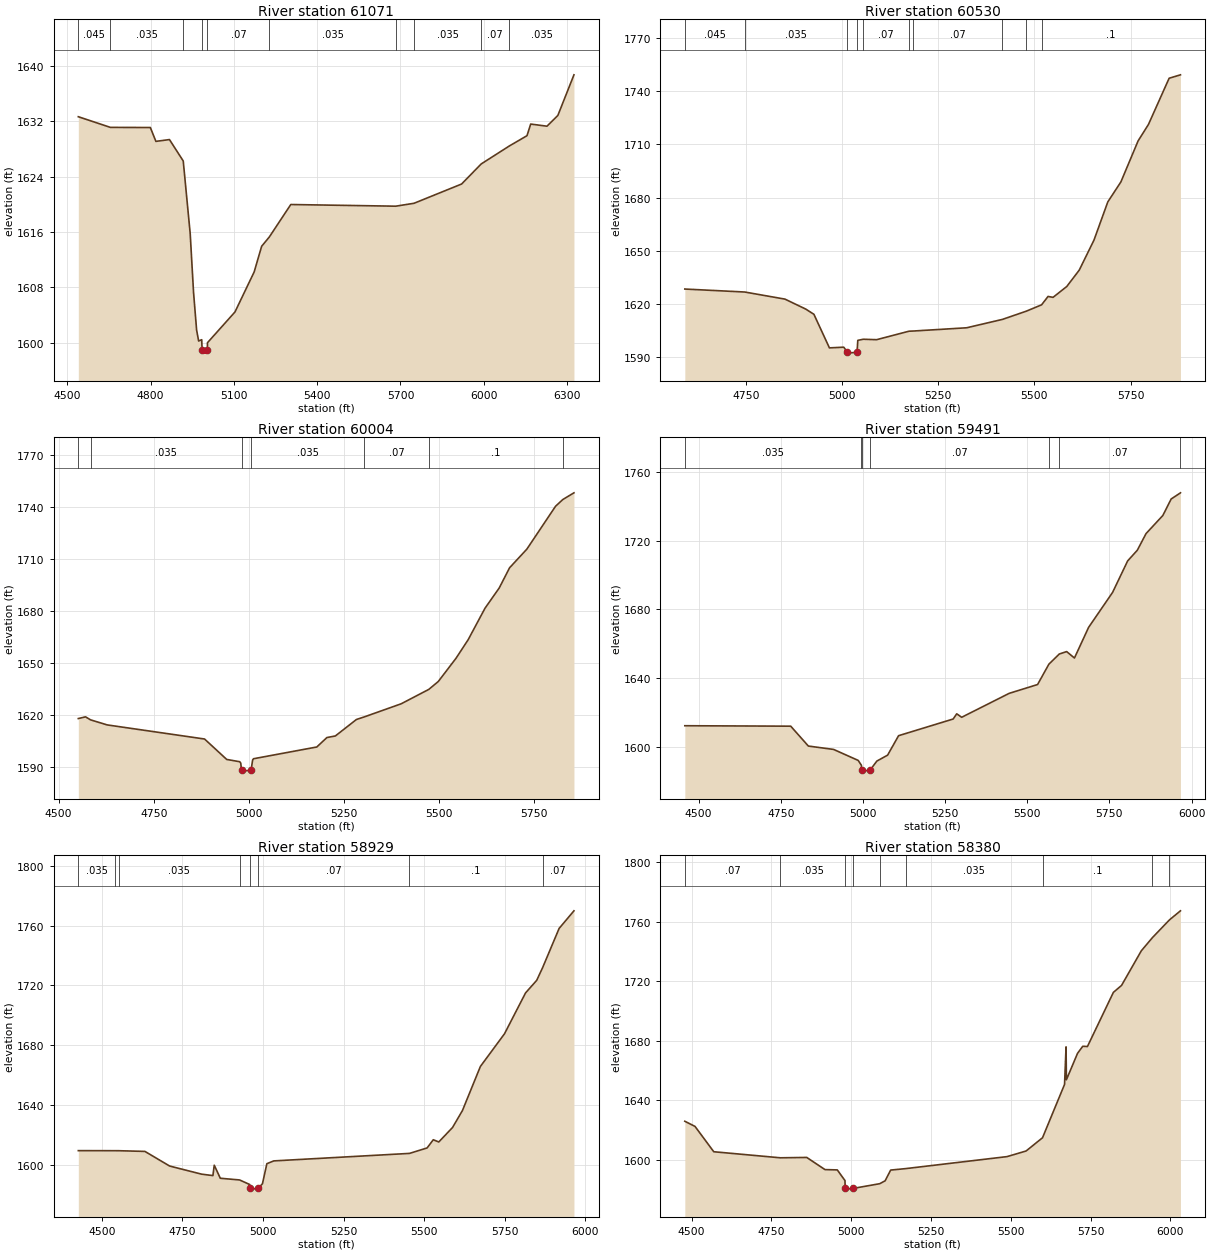
Type RM Length L Ch R = 1 ,61071   ,541,541,541
BEGIN DESCRIPTION:
Cypress Creek 78.0
END DESCRIPTION:
XS GIS Cut Line= 4
      1967351.94      13926840.1        1966975.       13926575.
        1966575.       13926575.      1965751.66     13926996.31
#Sta/Elev= 30
  4539.4 1632.66  4654.9 1631.12  4798.9  1631.1  4818.9  1629.1  4867.8 1629.36
  4917.4 1626.27  4942.5 1615.77  4954.6 1607.26  4965.6 1601.86  4972.9 1600.27
    4984 1600.46  4985.3 1599.02  4985.8 1598.52  5004.4 1599.02  5004.7 1600.02
  5103.9 1604.47  5172.9 1610.24  5199.9 1613.95  5227.5 1615.29  5304.9 1619.98
    5683 1619.74    5749 1620.16  5920.3 1622.94    5991 1625.84  6091.3 1628.41
  6155.9 1629.92  6169.3  1631.6  6227.9 1631.29  6267.1 1632.84  6325.1 1638.71
#Mann= 10 ,-1 , 0
  4539.4    .045       0  4654.9    .035       0  4917.4     .07       0
  4985.3     .05       0  5004.4     .07       0  5227.5    .035       0
    5683     .07       0    5749    .035       0    5991     .07       0
  6091.3    .035       0
Bank Sta=4985.3,5004.4
XS Rating Curve= 0 ,0
Exp/Cntr=0.3,0.1

Type RM Length L Ch R = 1 ,60530   ,526,526,526
BEGIN DESCRIPTION:
Cypress Creek 77.0
END DESCRIPTION:
XS GIS Cut Line= 3
        1967375.     13926574.98        1967325.       13926175.
      1966724.99     13925524.99
#Sta/Elev= 30
  4591.7 1628.34  4747.3 1626.66  4851.9 1622.65  4905.9 1617.02  4927.1 1614.07
  4967.4 1595.12  5004.6  1595.5  5014.2 1592.65  5014.7 1592.15  5039.2 1592.65
  5041.1 1599.36  5055.6 1599.99  5089.9 1599.74  5174.2 1604.53  5184.7 1604.62
  5323.8 1606.46  5416.8 1611.19  5478.6 1615.82  5518.6 1619.42  5535.4 1624.15
  5548.5 1623.66    5584 1629.77  5616.4    1639  5654.7 1655.95  5690.7 1677.56
  5724.7 1688.85  5769.3 1711.96  5796.3  1721.3    5850 1747.38  5879.4 1749.31
#Mann= 10 ,-1 , 0
  4591.7    .045       0  4747.3    .035       0  5014.2    .035       0
  5039.2    .035       0  5055.6     .07       0  5174.2    .035       0
  5184.7     .07       0  5416.8    .035       0  5478.6     .07       0
  5518.6      .1       0
Bank Sta=5014.2,5039.2
XS Rating Curve= 0 ,0
Exp/Cntr=0.3,0.1

Type RM Length L Ch R = 1 ,60004   ,513,513,513
BEGIN DESCRIPTION:
Cypress Creek 76.0
END DESCRIPTION:
XS GIS Cut Line= 3
        1967675.     13926224.97        1967625.       13925775.
      1966875.04     13925375.02
#Sta/Elev= 30
  4551.8 1618.03  4570.7 1619.01    4584 1617.28  4627.7 1614.36  4883.6 1606.23
  4941.9 1594.44    4976 1593.14  4978.7 1592.36  4980.8 1588.21  4981.3 1587.71
  5005.8 1588.21    5010 1594.16  5012.3 1594.85  5178.6 1601.63  5205.2 1607.08
  5227.4 1607.99  5282.8 1617.49  5303.6 1618.99  5400.3 1626.53  5472.9 1634.83
  5497.9 1639.38  5544.4 1652.75  5576.5 1663.51  5620.7 1681.64  5658.1 1693.33
  5685.3 1704.97  5730.7 1715.72  5806.1 1740.44  5825.2 1744.33  5854.5  1748.2
#Mann= 7 ,-1 , 0
  4551.8    .045       0    4584    .035       0  4980.8    .035       0
  5005.8    .035       0  5303.6     .07       0  5472.9      .1       0
  5825.2     .07       0
Bank Sta=4980.8,5005.8
XS Rating Curve= 0 ,0
Exp/Cntr=0.3,0.1

Type RM Length L Ch R = 1 ,59491   ,562,562,562
BEGIN DESCRIPTION:
Cypress Creek 75.0
END DESCRIPTION:
XS GIS Cut Line= 3
      1968193.21     13926035.19        1968025.       13925525.
      1967475.01     13924725.02
#Sta/Elev= 30
  4458.1 1612.18  4780.3 1611.92    4834 1600.34  4910.9 1598.37  4985.6 1591.98
  4995.4 1589.12  4996.3 1586.24  4996.8 1585.74  5021.4 1586.24  5042.4  1591.6
  5075.1 1595.05  5108.5 1606.38  5274.6  1616.1  5285.4 1619.11  5300.5 1617.11
  5445.1 1631.05  5531.4 1636.18  5565.8 1648.03  5597.4 1653.95  5619.8 1655.37
  5643.6 1651.63  5686.7 1669.49  5759.6 1689.83  5805.4 1708.16  5834.9 1714.42
  5861.4 1724.09  5912.5 1734.63  5937.9 1744.26  5965.9 1747.79  5966.1 1747.84
#Mann= 7 ,-1 , 0
  4458.1    .035       0  4995.4     .07       0  4996.3     .05       0
  5021.4     .07       0  5565.8      .1       0  5597.4     .07       0
  5965.9      .1       0
Bank Sta=4996.3,5021.4
XS Rating Curve= 0 ,0
Exp/Cntr=0.3,0.1

Type RM Length L Ch R = 1 ,58929   ,549,549,549
BEGIN DESCRIPTION:
Cypress Creek 74.0
END DESCRIPTION:
XS GIS Cut Line= 3
      1968568.88     13925795.11        1968475.       13925225.
      1967874.97     13924474.97
#Sta/Elev= 30
  4426.9 1609.53  4540.4 1609.49    4552 1609.48  4633.6 1609.02  4710.4 1599.23
  4809.9 1593.79  4844.6 1592.85  4848.8 1599.79  4867.6 1591.07  4927.5 1589.93
  4958.9 1586.88  4959.5  1584.3    4960  1583.8  4984.6  1584.3  4998.4 1587.39
  5012.1 1600.81  5033.5 1602.67  5454.6 1607.68  5509.4 1611.33  5528.6 1616.81
  5545.7 1615.33  5588.4 1625.02  5619.1 1636.33  5674.9 1665.84  5749.7 1687.68
    5815 1714.99  5849.6 1723.38  5868.1 1731.95  5919.2 1758.11  5965.2 1769.87
#Mann= 8 ,-1 , 0
  4426.9    .035       0  4540.4     .07       0    4552    .035       0
  4927.5     .07       0  4959.5     .05       0  4984.6     .07       0
  5454.6      .1       0  5868.1     .07       0
Bank Sta=4959.5,4984.6
XS Rating Curve= 0 ,0
Exp/Cntr=0.3,0.1

Type RM Length L Ch R = 1 ,58380   ,512,512,512
BEGIN DESCRIPTION:
Cypress Creek 73.0
END DESCRIPTION:
XS GIS Cut Line= 3
      1969075.01     13925525.04        1968925.       13925025.
      1968275.02     13924225.03
#Sta/Elev= 30
  4478.6 1625.97  4510.6 1622.49  4569.3 1605.51  4777.9 1601.44  4860.6 1601.69
  4917.8 1593.52  4956.3 1593.32  4980.4 1586.16    4981 1580.92  4981.5 1580.42
  5006.4 1580.92  5089.2 1584.06  5106.1 1585.99  5123.5  1593.2  5170.3 1594.18
  5488.2 1602.24  5547.9 1606.02  5599.3 1614.91  5668.3  1650.7    5673 1675.86
  5674.1 1653.81    5709 1671.55  5725.4 1676.29    5740 1676.12  5821.3 1712.46
  5846.9 1717.13  5908.8 1740.36  5943.8 1749.24  5996.9 1761.09  6031.4 1767.18
#Mann= 9 ,-1 , 0
  4478.6     .07       0  4777.9    .035       0    4981    .035       0
  5006.4    .035       0  5089.2     .07       0  5170.3    .035       0
  5599.3      .1       0  5943.8    .035       0  5996.9     .07       0
Bank Sta=4981,5006.4
XS Rating Curve= 0 ,0
Exp/Cntr=0.3,0.1

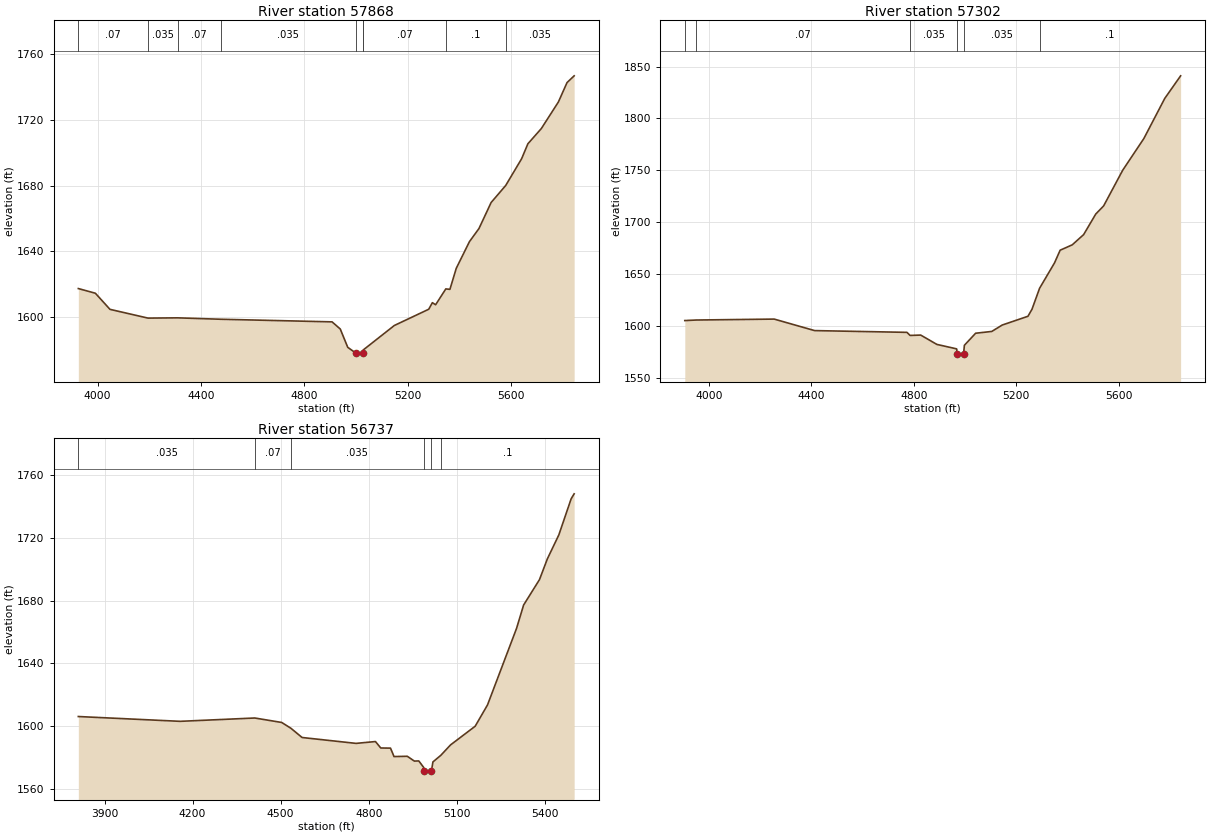
Type RM Length L Ch R = 1 ,57868   ,566,566,566
BEGIN DESCRIPTION:
Cypress Creek 72.0
END DESCRIPTION:
XS GIS Cut Line= 4
      1969281.38     13925640.32       1969389.8     13925174.85
        1969175.       13924625.      1968425.04     13924225.02
#Sta/Elev= 30
  3925.5 1617.48  3991.4 1614.64    4048 1604.85  4195.1 1599.54  4309.3  1599.7
    4476 1598.85  4907.1 1597.26  4938.8 1592.93  4967.8 1581.81  5000.1 1578.18
  5000.6 1577.68  5025.5 1578.18  5027.7 1580.21  5148.1 1595.07  5281.1 1604.92
  5295.2  1608.9  5307.7 1607.65  5347.2 1617.26  5363.1    1617  5387.6 1629.76
  5438.6 1645.94  5475.4  1653.9  5522.5  1669.7  5578.9 1680.04  5640.3 1696.22
  5664.7 1705.34  5716.8  1714.6  5782.7 1730.71  5816.2  1742.5  5843.7 1746.59
#Mann= 9 ,-1 , 0
  3925.5     .07       0  4195.1    .035       0  4309.3     .07       0
    4476    .035       0  5000.1    .035       0  5025.5    .035       0
  5027.7     .07       0  5347.2      .1       0  5578.9    .035       0
Bank Sta=5000.1,5025.5
XS Rating Curve= 0 ,0
Exp/Cntr=0.3,0.1

Type RM Length L Ch R = 1 ,57302   ,565,565,565
BEGIN DESCRIPTION:
Cypress Creek 71.0
END DESCRIPTION:
XS GIS Cut Line= 3
      1969972.33     13925367.48        1969625.       13924325.
      1969374.99     13923524.98
#Sta/Elev= 30
  3905.3 1605.34    3951 1605.86  4254.5 1606.76  4412.5 1595.67  4773.1 1593.98
  4785.5 1591.01  4826.9 1591.36  4890.1 1582.37    4966 1578.15  4967.6 1577.93
    4969 1573.51  4969.5 1573.01  4994.5 1573.51  4997.6 1581.55  5041.5 1593.14
  5104.5 1594.86  5145.4 1601.03  5245.9 1609.47  5261.7 1616.25  5291.4 1636.49
  5349.7 1660.91  5371.7 1673.12  5418.8 1678.27  5463.4 1688.14  5510.9 1707.99
  5541.4 1715.73  5616.2 1750.21  5698.6 1780.64  5780.3 1819.31  5842.3 1841.08
#Mann= 6 ,-1 , 0
  3905.3    .035       0    3951     .07       0  4785.5    .035       0
    4969     .05       0  4994.5    .035       0  5291.4      .1       0
Bank Sta=4969,4994.5
XS Rating Curve= 0 ,0
Exp/Cntr=0.3,0.1

Type RM Length L Ch R = 1 ,56737   ,545,545,545
BEGIN DESCRIPTION:
Cypress Creek 70.0
END DESCRIPTION:
XS GIS Cut Line= 4
      1970039.53     13925456.24      1970134.27     13924723.04
        1970175.       13924275.        1970175.     13923774.99
#Sta/Elev= 30
  3810.8 1606.17  4157.7 1603.11    4412 1605.23  4503.6 1602.39    4535  1598.7
  4573.1 1592.81  4756.8 1589.07  4823.1 1590.23  4841.2 1586.13  4874.3 1586.05
  4886.3 1580.67  4931.5 1580.85  4955.6  1577.8  4970.7 1577.89  4987.6 1573.69
    4988 1571.26  4988.5 1570.76  5013.6 1571.26  5018.8 1577.25  5045.7 1581.45
  5078.8 1588.08  5162.8 1599.99  5204.8 1613.55  5303.8 1662.33  5327.8 1677.18
  5381.8 1693.34  5408.8 1706.62  5447.8 1721.83  5489.8 1744.86    5500    1748
#Mann= 6 ,-1 , 0
  3810.8    .035       0    4412     .07       0    4535    .035       0
    4988    .035       0  5013.6    .035       0  5045.7      .1       0
Bank Sta=4988,5013.6
XS Rating Curve= 0 ,0
Exp/Cntr=0.3,0.1