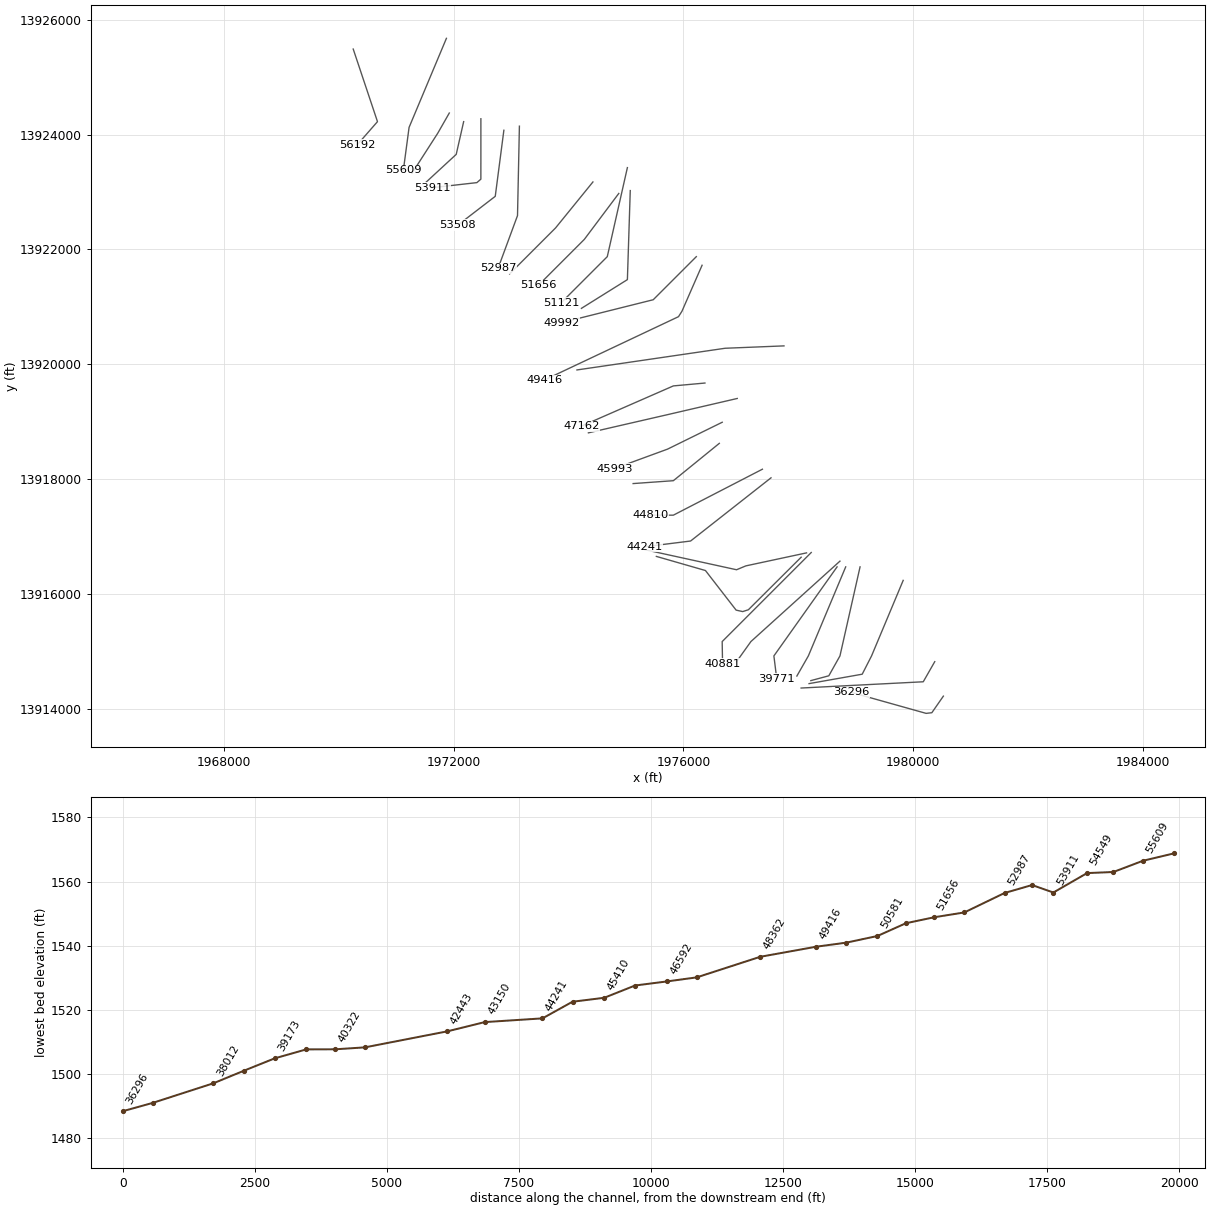
HEC-RAS study Cypress Creek.prj: Cypress Creek Base Level Engineering

--- Cypress Creek.g01 (geometry) --- (continued)

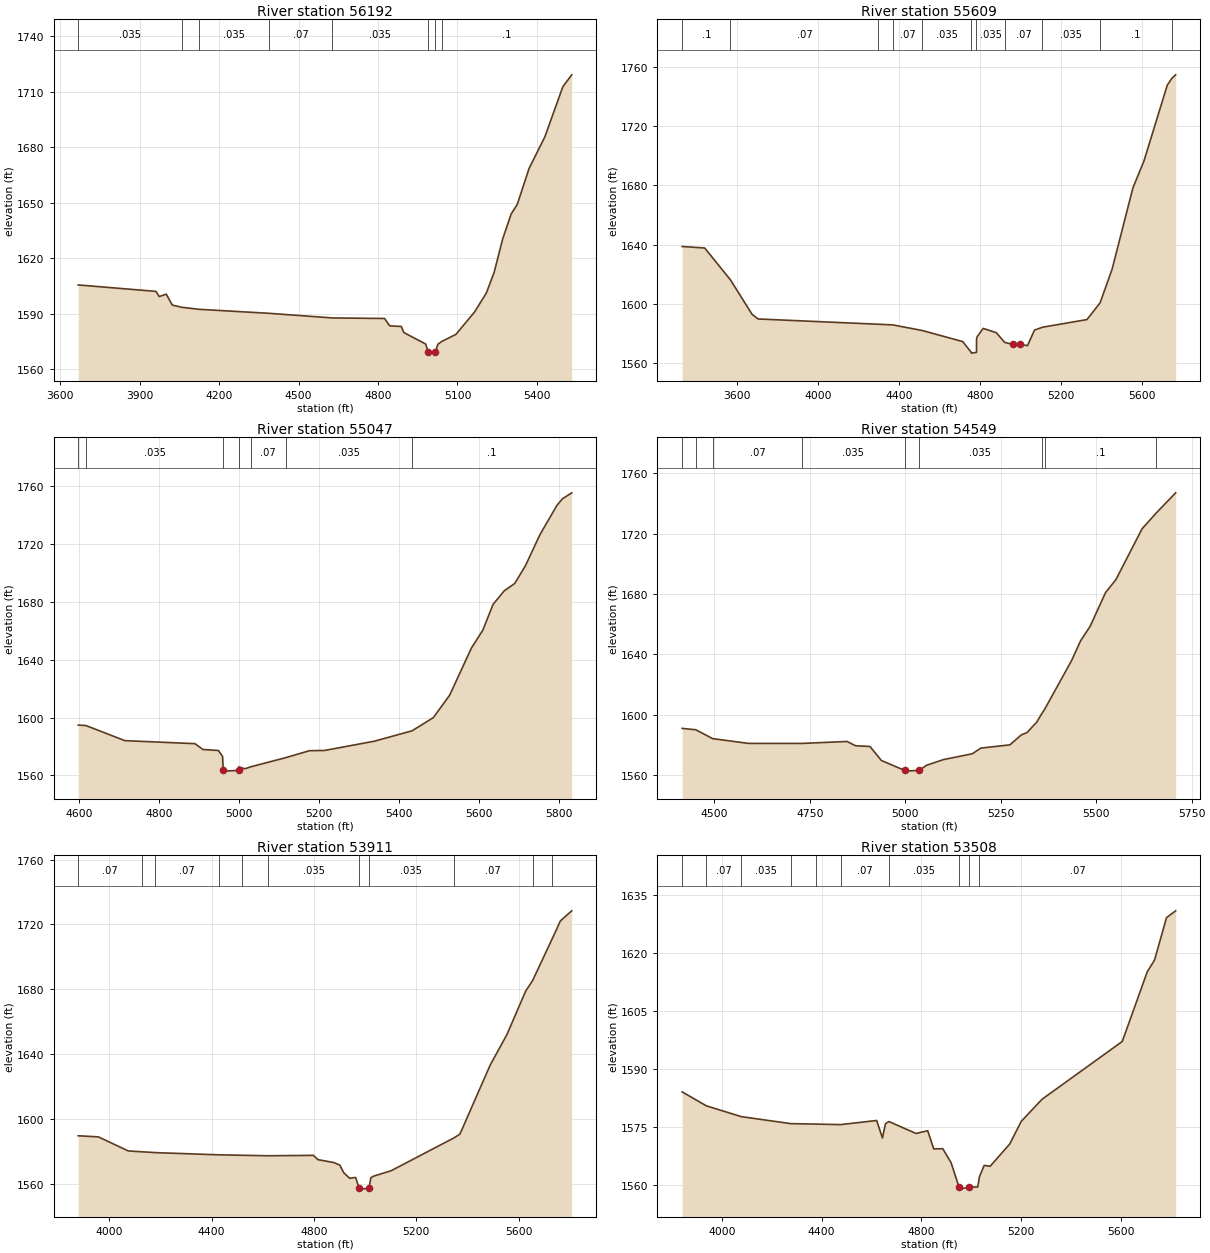
Type RM Length L Ch R = 1 ,56192   ,583,583,583
BEGIN DESCRIPTION:
Cypress Creek 69.0
END DESCRIPTION:
XS GIS Cut Line= 3
      1970252.64     13925488.48        1970675.       13924225.
      1970325.01     13923825.01
#Sta/Elev= 30
  3667.8 1605.62  3961.2 1602.13  3973.9 1599.32  4000.2 1600.64  4023.1 1594.74
  4059.5 1593.52  4124.9 1592.44  4386.6  1590.3    4628 1587.78  4824.8 1587.49
  4843.8 1583.53    4888 1583.16  4897.5 1579.88  4979.8 1573.71  4990.2 1569.27
  4990.7 1568.77  5015.8 1569.27  5026.3 1573.61  5042.1 1575.18  5094.1  1578.9
  5164.3 1590.94  5208.9 1601.21  5238.7 1612.52  5270.6 1630.39  5302.5 1643.87
  5325.9 1649.14  5370.5  1668.6    5430 1685.63  5498.1 1712.76  5531.5 1719.14
#Mann= 8 ,-1 , 0
  3667.8    .035       0  4059.5     .07       0  4124.9    .035       0
  4386.6     .07       0    4628    .035       0  4990.2    .035       0
  5015.8    .035       0  5042.1      .1       0
Bank Sta=4990.2,5015.8
XS Rating Curve= 0 ,0
Exp/Cntr=0.3,0.1

Type RM Length L Ch R = 1 ,55609   ,562,562,562
BEGIN DESCRIPTION:
Cypress Creek 68.0
END DESCRIPTION:
XS GIS Cut Line= 3
      1971875.01     13925675.03        1971225.       13924125.
      1971125.01     13923375.04
#Sta/Elev= 30
  3328.3 1638.68  3439.7 1637.67  3566.8 1616.13  3673.5  1592.8  3703.3 1589.62
  4297.6 1586.04  4369.3 1585.59  4513.8 1581.82    4714 1574.31  4756.4 1566.99
  4756.9 1566.49  4782.1 1566.99  4782.3 1575.88  4785.5 1577.64  4815.1 1583.23
  4879.9 1580.33  4921.5 1573.73  4961.6 1572.48  4998.3 1572.36  5034.1 1571.58
  5068.6 1582.09  5107.4 1584.01  5327.6 1589.21  5392.6 1600.54  5451.8 1623.29
  5554.7 1678.36  5609.2 1696.58  5724.2 1747.88  5747.7 1752.65  5765.7  1754.9
#Mann= 11 ,-1 , 0
  3328.3      .1       0  3566.8     .07       0  4297.6    .035       0
  4369.3     .07       0  4513.8    .035       0  4756.4     .05       0
  4782.1    .035       0  4921.5     .07       0  5107.4    .035       0
  5392.6      .1       0  5747.7     .07       0
#Block Obstruct= 2 , 0
         4815.05  1583.1
Bank Sta=4961.6,4998.3
XS Rating Curve= 0 ,0
Exp/Cntr=0.3,0.1

Type RM Length L Ch R = 1 ,55047   ,498,498,498
BEGIN DESCRIPTION:
Cypress Creek 67.0
END DESCRIPTION:
XS GIS Cut Line= 3
      1971924.98     13924374.96        1971725.       13924025.
      1971275.02     13923325.02
#Sta/Elev= 30
  4597.2 1594.79  4616.2 1594.49    4714 1584.04  4889.4 1581.95  4909.2 1577.94
  4948.2 1577.22  4958.6 1573.05  4960.1 1563.48  4961.1 1562.98  4998.6 1563.48
  4999.4 1565.96  5014.3 1564.58    5029 1565.95  5116.7  1572.3  5175.9 1577.09
    5214 1577.25  5338.9 1583.69  5432.6 1590.82  5485.7 1599.86  5526.9 1615.43
  5581.2 1647.93  5609.9 1660.36  5635.5 1678.14  5663.4 1687.51  5689.7 1692.59
  5716.9 1705.04  5752.6 1726.19  5795.4 1746.57  5809.1 1751.09  5832.4 1755.21
#Mann= 7 ,-1 , 0
  4597.2     .07       0  4616.2    .035       0  4960.1    .035       0
  4998.6    .035       0    5029     .07       0  5116.7    .035       0
  5432.6      .1       0
Bank Sta=4960.1,4998.6
XS Rating Curve= 0 ,0
Exp/Cntr=0.3,0.1

Type RM Length L Ch R = 1 ,54549   ,638,638,638
BEGIN DESCRIPTION:
Cypress Creek 66.0
END DESCRIPTION:
XS GIS Cut Line= 3
      1972175.01     13924225.03      1972045.57      13923655.2
      1971524.98     13923174.98
#Sta/Elev= 30
  4415.5 1590.96  4451.3 1590.06  4495.4 1584.17  4589.2 1581.01  4729.5    1581
  4847.4 1582.29  4869.6 1579.47  4907.6 1578.96  4937.3  1569.7    4998 1563.14
    4999 1562.64  5036.5 1563.14  5055.5 1566.51    5100 1570.28  5175.4 1574.14
  5197.9  1577.9  5274.1 1580.06  5303.7 1586.63  5318.7 1588.17  5344.2 1595.11
    5357 1600.51  5365.2 1603.72  5435.5 1635.88  5459.1 1648.98  5484.3 1658.68
  5524.4 1680.92  5551.5 1689.51  5620.2 1723.25  5657.4 1733.74  5708.1 1747.06
#Mann= 9 ,-1 , 0
  4415.5     .07       0  4451.3    .035       0  4495.4     .07       0
  4729.5    .035       0    4998    .035       0  5036.5    .035       0
    5357     .07       0  5365.2      .1       0  5657.4    .035       0
Bank Sta=4998,5036.5
XS Rating Curve= 0 ,0
Exp/Cntr=0.3,0.1

Type RM Length L Ch R = 1 ,53911   ,403,403,403
BEGIN DESCRIPTION:
Cypress Creek 65.0
END DESCRIPTION:
XS GIS Cut Line= 4
        1972475.       13924275.      1972474.71     13923223.59
      1972404.77     13923163.44      1971625.02       13923075.
#Sta/Elev= 30
  3879.1 1589.53  3957.9 1588.85  4074.9 1580.16  4129.1 1579.63  4179.9 1579.13
    4428 1577.77  4519.4 1577.49  4620.9 1577.19  4797.9 1577.44  4815.9 1574.79
  4878.9 1572.97  4901.6 1571.36  4916.6 1566.74  4939.8 1563.28  4963.2  1563.8
  4976.8 1557.09  4977.8 1556.59  5015.3 1557.09  5022.7 1563.61  5032.6 1564.56
    5102 1567.96  5346.6 1588.16  5370.7 1590.57  5489.2 1633.29  5554.3 1652.04
  5627.4  1678.8  5654.5 1685.33  5730.9 1711.05  5763.2  1722.2  5807.5 1728.42
#Mann= 11 ,-1 , 0
  3879.1     .07       0  4129.1    .035       0  4179.9     .07       0
    4428    .035       0  4519.4     .07       0  4620.9    .035       0
  4976.8    .035       0  5015.3    .035       0  5346.6     .07       0
  5654.5    .035       0  5730.9     .07       0
Bank Sta=4976.8,5015.3
XS Rating Curve= 0 ,0
Exp/Cntr=0.3,0.1

Type RM Length L Ch R = 1 ,53508   ,521,521,521
BEGIN DESCRIPTION:
Cypress Creek 64.0
END DESCRIPTION:
XS GIS Cut Line= 3
        1972875.     13924074.99        1972725.       13922925.
        1972075.       13922425.
#Sta/Elev= 30
  3840.3 1584.11  3937.8 1580.49  4077.4  1577.7  4276.6 1575.88  4376.2 1575.77
  4475.8 1575.63  4620.7  1576.7  4643.9 1572.16    4656 1575.86  4669.6 1576.43
  4778.6 1573.34  4825.4 1574.05  4849.6 1569.34  4885.9 1569.39  4919.2 1565.77
  4951.3 1559.42  4952.3 1558.92  4989.9 1559.42    5026 1559.47    5033 1562.13
    5052 1565.07  5075.7 1564.83  5154.6 1570.62  5200.6 1576.47  5283.9 1582.19
    5606 1597.17    5706 1615.19  5735.5 1618.27  5783.5 1629.26  5820.1 1631.01
#Mann= 10 ,-1 , 0
  3840.3    .035       0  3937.8     .07       0  4077.4    .035       0
  4276.6     .07       0  4376.2    .035       0  4475.8     .07       0
  4669.6    .035       0  4951.3    .035       0  4989.9    .035       0
    5033     .07       0
Bank Sta=4951.3,4989.9
XS Rating Curve= 0 ,0
Exp/Cntr=0.3,0.1

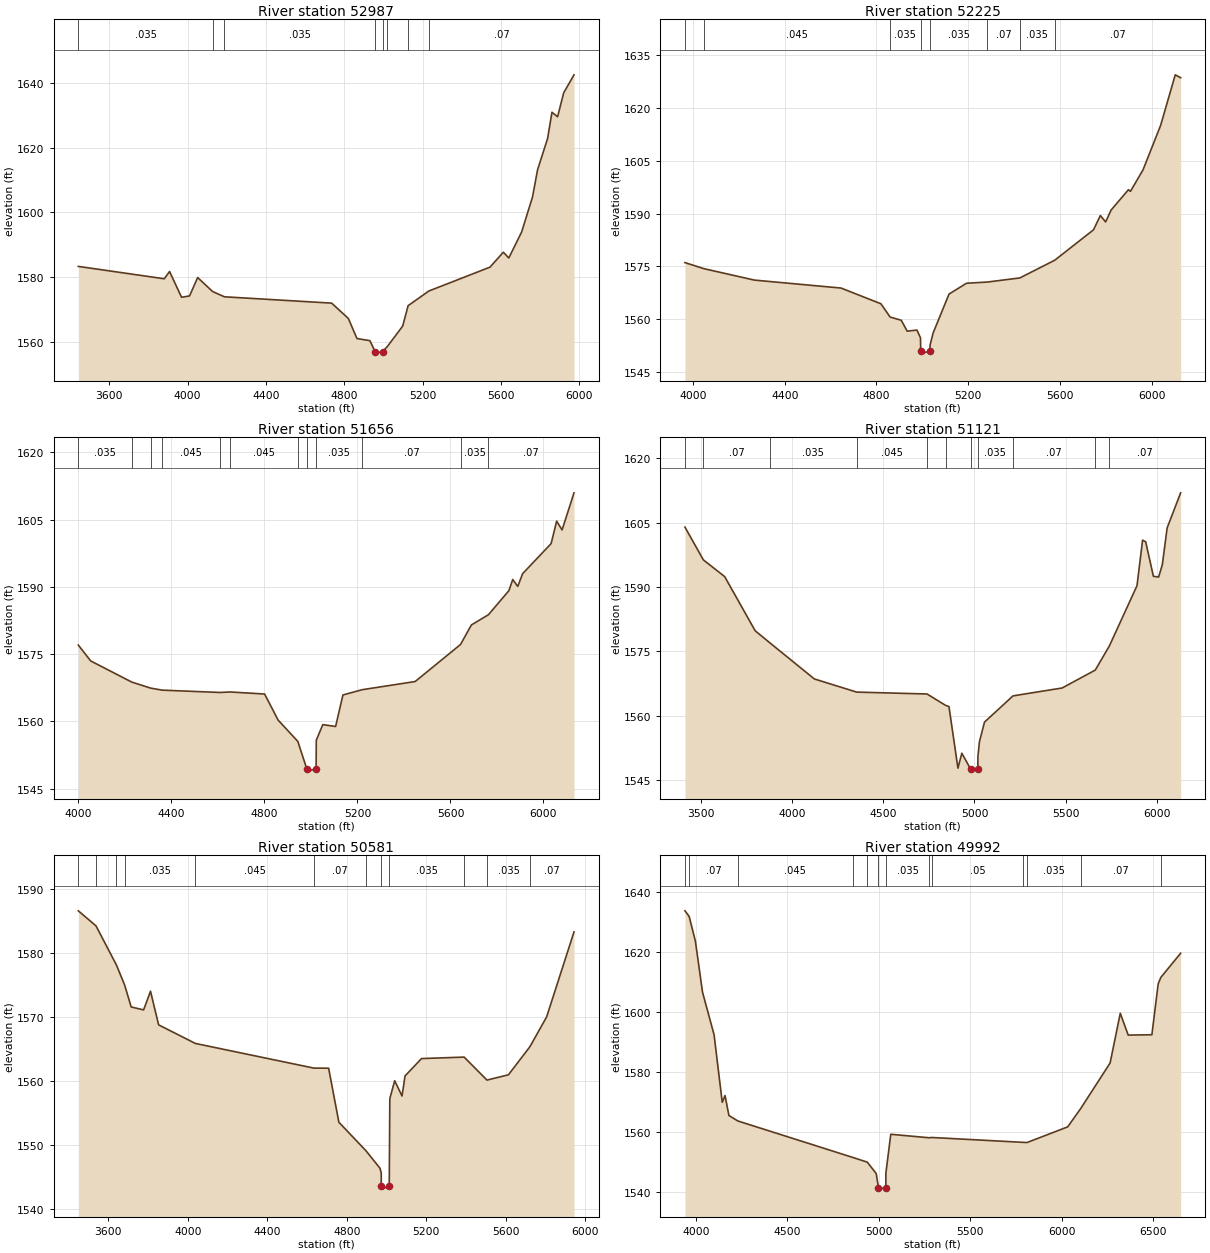
Type RM Length L Ch R = 1 ,52987   ,762,762,762
BEGIN DESCRIPTION:
Cypress Creek 63.0
END DESCRIPTION:
XS GIS Cut Line= 3
      1973145.43     13924146.09      1973112.36     13922589.43
      1972774.99     13921674.99
#Sta/Elev= 30
    3442 1583.26    3881 1579.43    3908 1581.68  3969.2 1573.72    4010 1574.12
  4051.5 1579.81  4127.8 1575.49  4188.2 1573.86  4736.1  1571.9  4821.3 1567.15
  4865.2 1560.95  4931.2  1560.3  4957.7 1556.94  4958.7 1556.44  4996.5 1556.94
  5020.3 1558.48  5098.8 1564.81  5126.4 1571.12  5232.4 1575.65  5544.6 1583.03
  5612.7 1587.64  5640.7 1585.87  5706.1 1593.88    5762 1604.77  5787.6 1613.14
  5838.8 1622.81  5861.1 1630.92  5889.9 1629.54    5921 1636.93  5973.7  1642.5
#Mann= 8 ,-1 , 0
    3442    .035       0  4127.8     .07       0  4188.2    .035       0
  4957.7    .035       0  4996.5    .035       0  5020.3      .1       0
  5126.4    .035       0  5232.4     .07       0
Bank Sta=4957.7,4996.5
XS Rating Curve= 0 ,0
Exp/Cntr=0.3,0.1

Type RM Length L Ch R = 1 ,52225   ,569,569,569
BEGIN DESCRIPTION:
Cypress Creek 62.0
END DESCRIPTION:
XS GIS Cut Line= 3
      1974425.02     13923175.02        1973775.       13922375.
      1972974.98     13921574.98
#Sta/Elev= 30
  3964.7 1576.09    4048 1574.36  4267.6 1571.12  4645.6 1568.86  4819.5  1564.4
  4859.7 1560.63  4908.3 1559.71  4934.2 1556.62  4976.7 1556.93  4992.2 1554.73
  4993.1 1550.88  4994.1 1550.38    5033 1550.88    5034 1552.67    5047 1556.05
  5116.7 1567.16  5193.1 1570.23  5284.2 1570.57  5425.8 1571.74  5577.8 1576.77
    5747 1585.41  5776.7 1589.46  5799.8 1587.64  5823.4 1590.99  5899.2 1596.79
    5908 1596.32  5963.1 1602.46  6039.8 1615.09  6103.4 1629.42  6126.9  1628.6
#Mann= 8 ,-1 , 0
  3964.7    .035       0    4048    .045       0  4859.7    .035       0
  4993.1    .035       0    5033    .035       0  5284.2     .07       0
  5425.8    .035       0  5577.8     .07       0
Bank Sta=4993.1,5033
XS Rating Curve= 0 ,0
Exp/Cntr=0.3,0.1

Type RM Length L Ch R = 1 ,51656   ,535,535,535
BEGIN DESCRIPTION:
Cypress Creek 61.0
END DESCRIPTION:
XS GIS Cut Line= 3
      1974874.99     13922974.98        1974275.       13922175.
      1973475.03     13921375.03
#Sta/Elev= 30
    4000 1577.01  4053.3 1573.47  4229.7 1568.76  4310.8 1567.41  4360.5 1566.96
  4608.7 1566.44  4652.1 1566.55    4801 1566.09  4859.2 1560.27  4943.7 1555.53
  4982.4 1549.39  4983.4 1548.89  5022.4 1549.39  5023.2 1555.79  5051.2 1559.26
  5106.3 1558.85  5137.7 1565.88  5220.9 1567.06  5448.3 1568.88  5643.3 1577.14
  5690.1  1581.5  5763.3 1583.78  5851.3 1589.15  5867.9 1591.64  5889.5  1590.1
  5910.3 1592.94  6032.9 1599.65  6056.7 1604.67    6080  1602.7  6131.3 1610.98
#Mann= 12 ,-1 , 0
    4000    .035       0  4229.7    .045       0  4310.8    .035       0
  4360.5    .045       0  4608.7    .035       0  4652.1    .045       0
  4943.7    .035       0  4982.4    .035       0  5022.4    .035       0
  5220.9     .07       0  5643.3    .035       0  5763.3     .07       0
Bank Sta=4982.4,5022.4
XS Rating Curve= 0 ,0
Exp/Cntr=0.3,0.1

Type RM Length L Ch R = 1 ,51121   ,540,540,540
BEGIN DESCRIPTION:
Cypress Creek 60.0
END DESCRIPTION:
XS GIS Cut Line= 3
      1975024.99     13923424.96        1974675.       13921875.
      1973874.97     13921074.97
#Sta/Elev= 30
    3411 1603.97  3512.2 1596.32  3629.1 1592.42  3796.3 1579.79  3876.9 1576.97
  4121.2 1568.54  4353.4 1565.47  4739.7 1565.03  4841.2 1562.38    4860  1562.1
  4909.2 1547.73  4930.7 1551.21  4978.6 1547.53  4979.6 1547.03  5018.6 1547.53
  5018.9 1550.46  5027.4 1553.93  5055.1 1558.47  5211.4 1564.59  5481.4 1566.43
  5662.9 1570.61  5740.1 1576.22  5891.9 1590.29  5922.6 1600.93  5939.6 1600.54
    5982 1592.49  6010.7 1592.32  6030.9 1595.19  6057.4 1603.78  6131.4 1611.97
#Mann= 11 ,-1 , 0
    3411    .035       0  3512.2     .07       0  3876.9    .035       0
  4353.4    .045       0  4739.7     .07       0  4841.2    .035       0
  4978.6    .035       0  5018.6    .035       0  5211.4     .07       0
  5662.9    .035       0  5740.1     .07       0
Bank Sta=4978.6,5018.6
XS Rating Curve= 0 ,0
Exp/Cntr=0.3,0.1

Type RM Length L Ch R = 1 ,50581   ,589,589,589
BEGIN DESCRIPTION:
Cypress Creek 59.0
END DESCRIPTION:
XS GIS Cut Line= 3
        1975075.     13923025.04        1975025.       13921475.
      1974225.04     13920975.03
#Sta/Elev= 30
  3448.9 1586.62    3538 1584.26  3640.8 1578.13  3681.9 1575.01  3714.9 1571.57
  3777.3 1571.11  3812.2 1574.03  3852.9 1568.77  4037.7 1565.86  4633.5    1562
  4708.4 1561.98    4760 1553.52  4896.5 1549.05  4967.1 1546.31  4973.1 1545.56
  4973.3 1543.55  4974.3 1543.05  5013.4 1543.55  5016.2 1556.95  5016.7 1557.26
  5040.7 1560.02  5077.7 1557.63  5092.9 1560.77  5175.7 1563.49  5390.3 1563.72
  5505.2 1560.12  5613.2 1560.95  5721.1 1565.34  5805.2    1570  5943.1 1583.32
#Mann= 12 ,-1 , 0
  3448.9     .07       0    3538    .035       0  3640.8     .07       0
  3681.9    .035       0  4037.7    .045       0  4633.5     .07       0
  4896.5    .035       0  4973.3    .035       0  5013.4    .035       0
  5390.3     .07       0  5505.2    .035       0  5721.1     .07       0
Bank Sta=4973.3,5013.4
XS Rating Curve= 0 ,0
Exp/Cntr=0.3,0.1

Type RM Length L Ch R = 1 ,49992   ,576,576,576
BEGIN DESCRIPTION:
Cypress Creek 58.0
END DESCRIPTION:
XS GIS Cut Line= 3
      1976224.98     13921874.98        1975475.       13921125.
      1973874.97     13920724.99
#Sta/Elev= 30
  3939.6 1633.88  3962.6 1632.03  3996.7 1623.76  4035.7 1606.72  4098.9 1592.51
  4143.5 1569.97  4158.8 1572.22    4180 1565.56  4228.9 1563.73  4857.7 1551.55
  4936.4 1549.99  4985.3 1546.18  4997.5 1541.48  4998.5 1540.98  5037.9 1541.48
  5038.1 1546.31  5064.9 1559.29  5275.6 1558.12  5289.4 1558.22  5786.7  1556.6
  5810.1 1556.54    6032 1561.76  6103.9 1567.94  6263.9 1583.08  6319.6 1599.68
  6362.9  1592.4  6492.3 1592.51  6526.8 1609.49  6541.6 1611.68  6649.5 1619.72
#Mann= 13 ,-1 , 0
  3939.6      .1       0  3962.6     .07       0  4228.9    .045       0
  4857.7     .07       0  4936.4    .035       0  4997.5    .035       0
  5037.9    .035       0  5275.6     .07       0  5289.4     .05       0
  5786.7     .07       0  5810.1    .035       0  6103.9     .07       0
  6541.6    .035       0
Bank Sta=4997.5,5037.9
XS Rating Curve= 0 ,0
Exp/Cntr=0.3,0.1

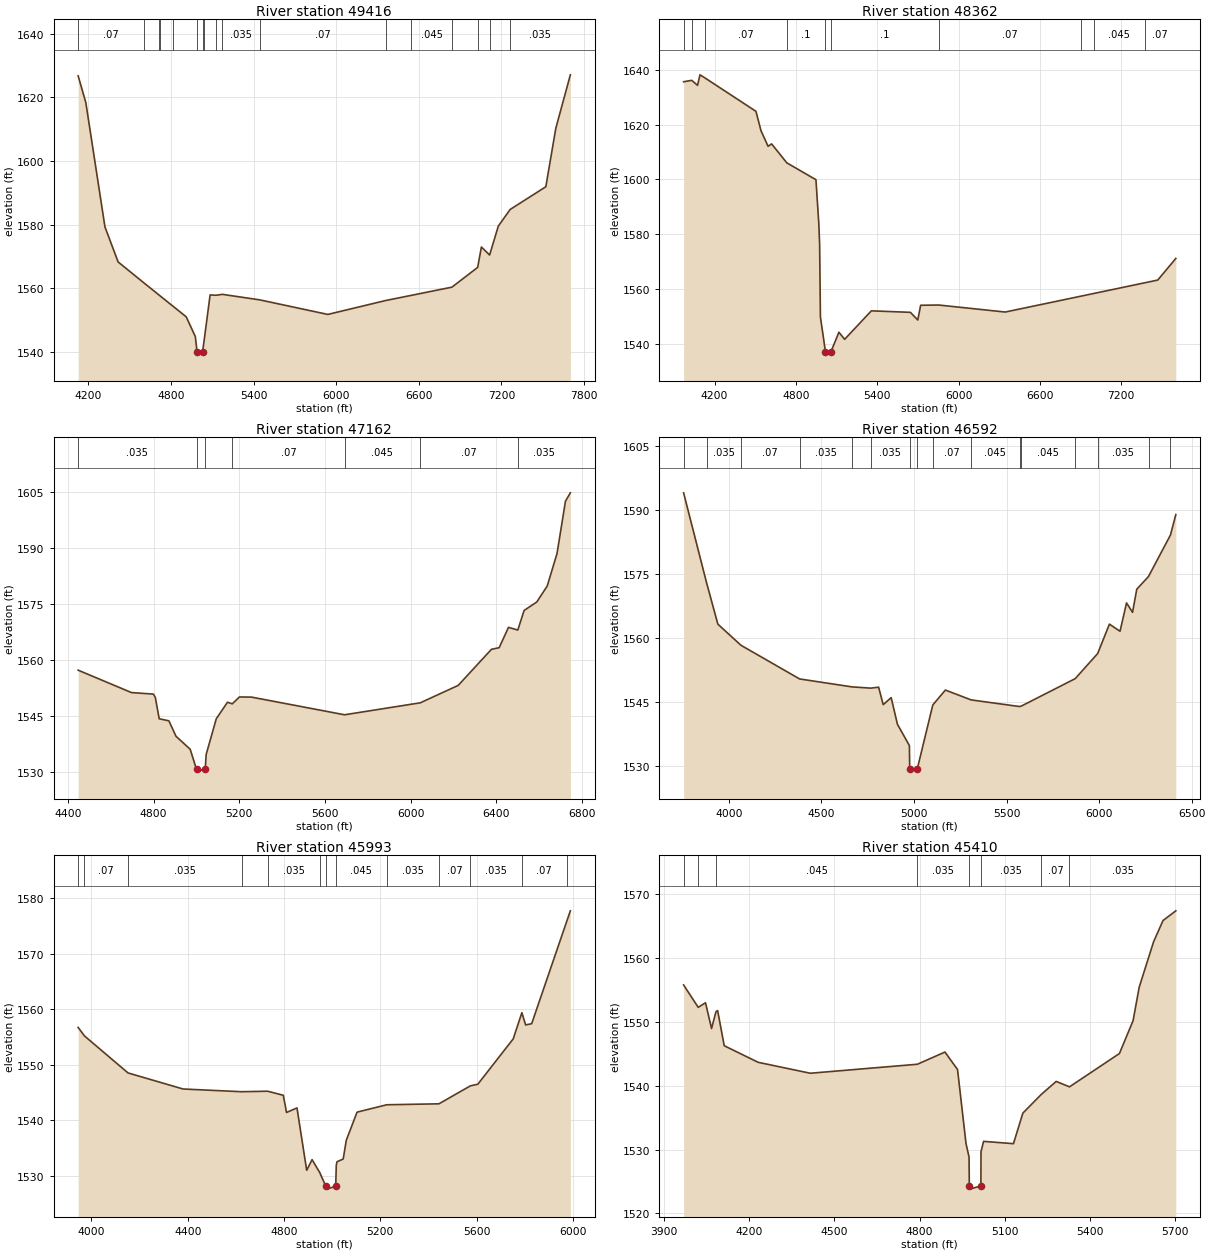
Type RM Length L Ch R = 1 ,49416   ,1054,1054,1054
BEGIN DESCRIPTION:
Cypress Creek 57.0
END DESCRIPTION:
XS GIS Cut Line= 4
      1976324.99     13921724.98        1975975.       13920925.
      1975914.54     13920830.21      1973574.98     13919724.99
#Sta/Elev= 30
  4126.9 1626.74  4182.6 1618.36  4321.6  1579.3  4417.2 1568.32  4604.1 1561.76
    4713 1557.98  4722.1 1557.66  4814.6 1554.45  4911.6 1551.09  4977.6 1544.88
  4989.9  1540.2  4990.9  1539.7  5030.3  1540.2  5043.2 1544.26  5084.8 1557.97
    5128 1557.86  5174.2 1558.15  5444.7 1556.42  5939.3 1551.85    6360 1556.22
    6546 1557.84  6840.2 1560.41  7027.2 1566.61  7054.1 1573.01  7113.8  1570.5
  7176.8 1579.56    7263  1584.8  7521.9 1591.93  7594.4  1610.3    7700 1627.06
#Mann= 17 ,-1 , 0
  4126.9     .07       0  4604.1    .045       0    4713    .035       0
  4722.1    .045       0  4814.6     .07       0  4989.9     .05       0
  5030.3     .07       0  5043.2    .035       0    5128     .07       0
  5174.2    .035       0  5444.7     .07       0    6360     .05       0
    6546    .045       0  6840.2     .07       0  7027.2    .035       0
  7113.8     .07       0    7263    .035       0
Bank Sta=4989.9,5030.3
XS Rating Curve= 0 ,0
Exp/Cntr=0.3,0.1

Type RM Length L Ch R = 1 ,48362   ,1200,1200,1200
BEGIN DESCRIPTION:
Cypress Creek 56.0
END DESCRIPTION:
XS GIS Cut Line= 3
      1977750.82     13920321.64      1976726.27     13920280.37
      1974147.02      13919902.9
#Sta/Elev= 30
  3971.3  1635.7  4031.3 1636.22  4074.2 1634.39  4092.2 1638.23  4129.8 1637.07
  4505.1  1624.9  4542.6 1617.79  4594.6 1612.12  4620.6    1613  4733.2 1606.07
  4947.9 1599.92  4968.9 1583.96  4974.9 1576.61  4980.9 1549.76  5018.1 1537.07
  5019.1 1536.57  5058.7 1537.07  5117.2  1544.2  5159.7 1541.62  5356.7 1552.02
  5644.8 1551.47  5699.3 1548.67  5720.5 1554.05  5853.6 1554.14  6344.7 1551.58
    6901 1557.35  7000.2 1558.38  7374.1 1562.26    7470 1563.26  7603.4 1571.15
#Mann= 10 ,-1 , 0
  3971.3    .094       0  4031.3    .035       0  4129.8     .07       0
  4733.2      .1       0  5018.1     .05       0  5058.7      .1       0
  5853.6     .07       0    6901     .05       0  7000.2    .045       0
  7374.1     .07       0
Bank Sta=5018.1,5058.7
XS Rating Curve= 0 ,0
Exp/Cntr=0.3,0.1

Type RM Length L Ch R = 1 ,47162   ,570,570,570
BEGIN DESCRIPTION:
Cypress Creek 55.0
END DESCRIPTION:
XS GIS Cut Line= 3
      1976375.01       13919675.        1975825.       13919625.
      1974225.01       13918925.
#Sta/Elev= 30
  4447.7 1557.26  4696.7 1551.25  4799.1 1550.84  4808.2 1549.93  4826.3 1544.21
  4871.4 1543.68  4904.6 1539.53  4970.9 1536.04  5000.4 1530.67  5001.4 1530.17
  5041.1 1530.67  5045.7 1534.68  5092.7 1544.21  5145.1 1548.66  5167.4 1548.23
  5200.8 1550.07  5256.5 1550.04  5691.9 1545.29  6045.4  1548.5  6222.5 1553.17
  6377.7 1562.85  6413.8 1563.29  6457.4 1568.75    6501 1568.03  6530.3 1573.28
  6589.5 1575.55  6638.3 1579.84  6684.2 1588.59  6723.5 1602.61  6746.4 1604.85
#Mann= 7 ,-1 , 0
  4447.7    .035       0  5000.4    .035       0  5041.1    .035       0
  5167.4     .07       0  5691.9    .045       0  6045.4     .07       0
    6501    .035       0
Bank Sta=5000.4,5041.1
XS Rating Curve= 0 ,0
Exp/Cntr=0.3,0.1

Type RM Length L Ch R = 1 ,46592   ,599,599,599
BEGIN DESCRIPTION:
Cypress Creek 54.0
END DESCRIPTION:
XS GIS Cut Line= 3
      1976937.35     13919406.37        1975725.       13919125.
      1974346.34     13918808.05
#Sta/Elev= 30
  3755.4 1593.95  3879.9 1572.86  3940.5 1563.25  4065.3 1558.31  4382.1 1550.44
    4666 1548.58  4766.4 1548.29    4809 1548.51  4833.7 1544.43  4876.8 1546.07
  4910.7 1539.84  4975.3 1534.86    4977 1529.39    4978 1528.89  5017.7 1529.39
  5101.7 1544.36  5169.7 1547.84  5308.7 1545.54  5570.3 1543.99  5580.5 1544.11
  5871.1 1550.51  5992.4 1556.38  6055.8 1563.25  6113.2 1561.59  6148.3 1568.21
  6180.8 1566.02  6203.6 1571.41    6267 1574.39  6385.6 1584.09  6414.6 1588.86
#Mann= 16 ,-1 , 0
  3755.4     .07       0  3879.9    .035       0  4065.3     .07       0
  4382.1    .035       0    4666     .07       0  4766.4    .035       0
    4977    .035       0  5017.7    .035       0  5101.7     .07       0
  5308.7    .045       0  5570.3     .07       0  5580.5    .045       0
  5871.1     .07       0  5992.4    .035       0    6267     .07       0
  6385.6    .035       0
Bank Sta=4977,5017.7
XS Rating Curve= 0 ,0
Exp/Cntr=0.3,0.1

Type RM Length L Ch R = 1 ,45993   ,583,583,583
BEGIN DESCRIPTION:
Cypress Creek 53.0
END DESCRIPTION:
XS GIS Cut Line= 3
      1976675.71     13918992.45        1975725.       13918525.
      1974800.08     13918186.01
#Sta/Elev= 30
  3944.7 1556.76    3971 1555.23    4152 1548.56  4380.6 1545.67  4623.7 1545.18
  4731.8 1545.27  4796.8 1544.54  4810.2 1541.44  4853.7 1542.26    4894 1531.02
  4916.3 1532.94  4948.2 1530.62  4973.7 1528.13  4974.7 1527.63  5014.5 1528.13
  5016.9 1531.93    5020 1532.57  5045.6 1533.05  5058.4 1536.42  5103.2  1541.5
  5226.6 1542.83  5443.3    1543  5573.6 1546.23  5604.8 1546.53  5751.8  1554.7
  5787.8 1559.42  5803.3 1557.21  5828.5 1557.44  5974.1 1575.87  5989.2 1577.77
#Mann= 13 ,-1 , 0
  3944.7    .035       0    3971     .07       0    4152    .035       0
  4623.7     .07       0  4731.8    .035       0  4948.2    .045       0
  4973.7    .045       0  5014.5    .045       0  5226.6    .035       0
  5443.3     .07       0  5573.6    .035       0  5787.8     .07       0
  5974.1    .035       0
Bank Sta=4973.7,5014.5
XS Rating Curve= 0 ,0
Exp/Cntr=0.3,0.1

Type RM Length L Ch R = 1 ,45410   ,600,600,600
BEGIN DESCRIPTION:
Cypress Creek 52.0
END DESCRIPTION:
XS GIS Cut Line= 3
      1976625.02     13918625.02        1975825.       13917975.
      1975124.99       13917925.
#Sta/Elev= 30
  3969.2 1555.79  4020.7 1552.28  4046.3    1553  4067.6 1548.97  4083.2 1551.61
    4089 1551.78  4112.2 1546.27  4231.8 1543.67  4415.2 1541.96  4792.1 1543.37
  4889.2 1545.28  4933.5 1542.54  4963.3 1530.94    4974 1528.84  4974.9 1524.31
  4975.9 1523.81  5015.7 1524.31    5016 1529.66  5025.1 1531.29  5130.3 1530.93
  5163.4 1535.72  5228.9 1538.67  5280.7 1540.68  5327.5 1539.83  5503.3 1545.05
  5551.4  1550.2  5572.9 1555.44  5623.6 1562.56  5656.7 1565.88  5701.8  1567.4
#Mann= 8 ,-1 , 0
  3969.2     .07       0  4020.7    .035       0  4083.2    .045       0
  4792.1    .035       0  4974.9    .035       0  5015.7    .035       0
  5228.9     .07       0  5327.5    .035       0
Bank Sta=4974.9,5015.7
XS Rating Curve= 0 ,0
Exp/Cntr=0.3,0.1

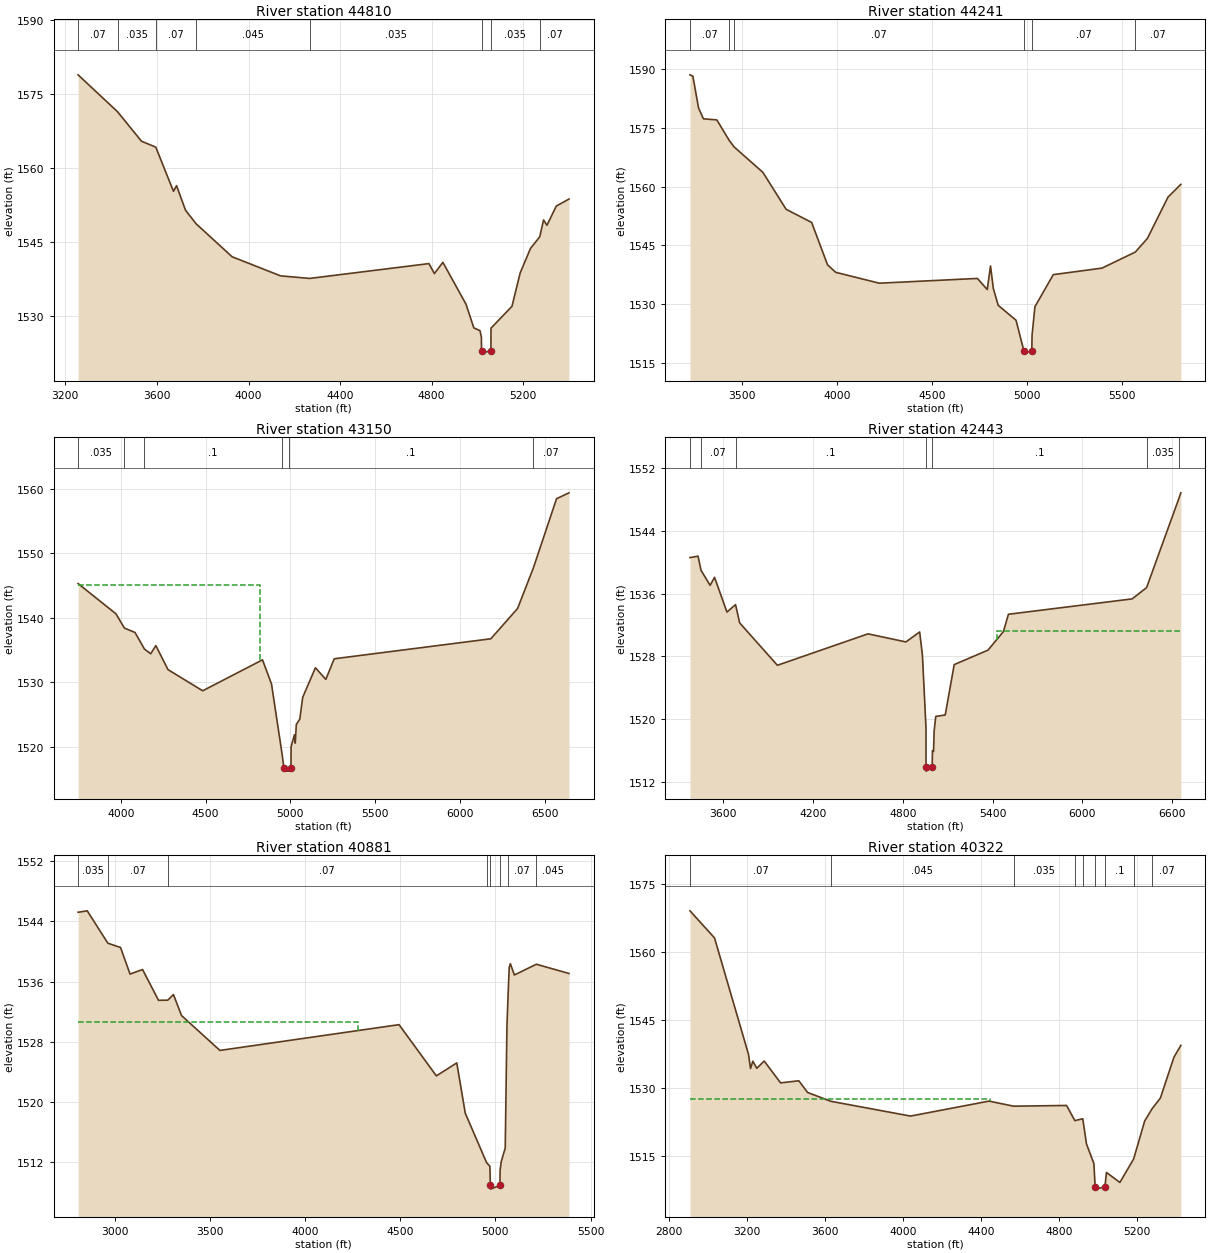
Type RM Length L Ch R = 1 ,44810   ,569,569,569
BEGIN DESCRIPTION:
Cypress Creek 51.0
END DESCRIPTION:
XS GIS Cut Line= 3
      1977375.03     13918175.01        1975825.       13917375.
      1975425.01       13917375.
#Sta/Elev= 30
  3255.6 1578.84  3428.1 1571.37  3532.5 1565.42    3595 1564.22  3672.3 1555.29
  3685.7 1556.43  3724.9 1551.47  3770.9 1548.74  3928.4 1542.06  4140.1  1538.2
    4267 1537.68  4788.3 1540.68    4812 1538.66  4849.1 1540.93  4950.4 1532.45
  4984.1  1527.7  5011.3 1527.11  5017.3 1525.82  5017.8 1523.08  5018.8 1522.58
  5058.9 1523.08  5059.3 1527.63  5150.9 1532.04  5186.9 1538.81  5231.9 1543.75
  5272.1 1546.09  5288.9 1549.49  5303.9 1548.43  5344.3  1552.3  5399.9 1553.73
#Mann= 8 ,-1 , 0
  3255.6     .07       0  3428.1    .035       0    3595     .07       0
  3770.9    .045       0    4267    .035       0  5017.8    .035       0
  5058.9    .035       0  5272.1     .07       0
Bank Sta=5017.8,5058.9
XS Rating Curve= 0 ,0
Exp/Cntr=0.3,0.1

Type RM Length L Ch R = 1 ,44241   ,1091,1091,1091
BEGIN DESCRIPTION:
Cypress Creek 50.0
END DESCRIPTION:
XS GIS Cut Line= 3
      1977524.97     13918024.98        1976125.       13916925.
      1975325.04     13916825.01
#Sta/Elev= 30
  3224.7 1588.56  3239.9 1588.22  3269.8 1580.11  3295.5 1577.31  3366.1 1577.04
  3431.4  1571.8  3457.4 1570.12  3608.9 1563.62  3731.3 1554.18  3865.9 1550.81
  3949.6 1539.98  3992.5 1538.06  4222.7 1535.28  4739.3  1536.5    4791 1533.66
  4808.3 1539.69  4823.1 1533.95  4848.7 1529.63  4942.7 1525.81  4984.6  1517.9
  4985.6  1517.4  5025.7  1517.9  5027.3 1522.05  5042.4 1529.28  5139.1 1537.47
  5396.1 1539.14  5571.5 1543.25    5635 1546.73  5743.6  1557.3  5811.3 1560.56
#Mann= 6 ,-1 , 0
  3224.7     .07       0  3431.4    .035       0  3457.4     .07       0
  4984.6     .05       0  5025.7     .07       0  5571.5     .07       0
Bank Sta=4984.6,5025.7
XS Rating Curve= 0 ,0
Exp/Cntr=0.3,0.1

Type RM Length L Ch R = 1 ,43150   ,707,707,707
BEGIN DESCRIPTION:
Cypress Creek 49.0
END DESCRIPTION:
XS GIS Cut Line= 4
       1978143.2      13916718.6      1977087.13     13916492.39
        1976925.       13916425.      1975325.03     13916774.99
#Sta/Elev= 30
  3748.5 1545.31  3971.6 1540.62  4021.81538.405  4084.1 1537.73  4139.61535.158
  4176.4 1534.43  4206.9 1535.69  4278.5 1531.97    4483 1528.69  4835.5 1533.49
  4888.6 1529.74  4950.61518.931  4961.7 1516.74  4962.7 1516.24    4992 1516.24
  5003.1 1516.74  5004.1 1520.04  5023.5 1521.87  5028.6 1520.58  5034.8 1523.47
  5055.3  1524.3  5072.5 1527.68  5147.4 1532.26  5208.8 1530.46  5258.2 1533.65
  6181.3 1536.75  6338.9 1541.44  6432.11547.733  6568.5 1558.45  6641.9 1559.37
#Mann= 6 ,-1 , 0
  3748.5    .035       0  4021.8    .035       0  4139.6      .1       0
  4950.6     .05       0    4992      .1       0  6432.1     .07       0
#XS Ineff= 2 , 0
         4820.63 1545.04
Permanent Ineff=
       F       F
Bank Sta=4961.7,5003.1
XS Rating Curve= 0 ,0
Exp/Cntr=0.3,0.1

Type RM Length L Ch R = 1 ,42443   ,1562,1562,1562
BEGIN DESCRIPTION:
Cypress Creek 48.1
END DESCRIPTION:
XS GIS Cut Line= 6
      1978049.71     13916643.08       1977130.8     13915728.49
      1977032.12     13915696.82      1976917.57     13915722.28
      1976383.75     13916411.56      1975529.49     13916657.19
#Sta/Elev= 30
  3378.9 1540.61  3432.8 1540.79  3452.6 1538.99  3513.4 1537.07  3543.1 1538.09
  3625.8 1533.66  3683.2 1534.61  3710.7 1532.28  3962.6 1526.87  4567.7 1530.88
  4821.1 1529.85  4912.8 1531.12  4931.4 1528.13  4955.1 1518.88  4955.2 1513.87
  4956.2 1513.37  4996.6 1513.87  4998.1 1515.99  5005.6 1515.88  5009.3 1518.45
  5020.4 1520.35  5083.5 1520.53  5143.5 1526.96  5368.9  1528.8  5472.1 1531.17
  5505.6 1533.38    6332 1535.34  6428.2 1536.78  6645.7 1548.24  6657.2 1548.87
#Mann= 7 ,-1 , 0
  3378.9    .035       0  3452.6     .07       0  3683.2      .1       0
  4955.2     .05       0  4996.6      .1       0  6428.2    .035       0
  6645.7     .07       0
#XS Ineff= 2 , 0
         4881.39 1529.98 5427.96         1531.24
Permanent Ineff=
       F       F
Bank Sta=4955.2,4996.6
XS Rating Curve= 0 ,0
Exp/Cntr=0.3,0.1

Type RM Length L Ch R = 1 ,40881   ,559,559,559
BEGIN DESCRIPTION:
Cypress Creek 48.0
END DESCRIPTION:
XS GIS Cut Line= 3
      1978225.01     13916725.01        1976675.       13915175.
      1976681.51      13914788.8
#Sta/Elev= 30
    2808 1545.22  2856.1 1545.41  2964.5  1541.1    3031 1540.53  3080.9 1536.99
  3146.6  1537.6  3230.4  1533.5  3279.2 1533.52  3308.9 1534.27  3351.4 1531.47
  3552.9 1526.83  4493.7 1530.26  4689.9 1523.44    4797 1525.17  4841.6 1518.48
  4953.9 1511.88  4970.9 1511.42  4973.5 1508.87  4974.5 1508.37  5023.7 1508.87
  5024.5  1510.9  5030.5 1512.02  5051.5 1513.84  5060.5 1530.06  5066.7 1534.35
  5072.5 1537.89  5078.5 1538.37  5099.5 1536.87  5215.1  1538.3  5386.3 1537.07
#Mann= 8 ,-1 , 0
    2808    .035       0  2964.5     .07       0  3279.2     .07       0
  4953.9      .1       0  4973.5     .05       0  5023.7      .1       0
  5066.7     .07       0  5215.1    .045       0
#XS Ineff= 2 , 0
         4275.78 1530.63
Permanent Ineff=
       F       F
Bank Sta=4973.5,5023.7
XS Rating Curve= 0 ,0
Exp/Cntr=0.3,0.1

Type RM Length L Ch R = 1 ,40322   ,551,551,551
BEGIN DESCRIPTION:
Cypress Creek 47.0
END DESCRIPTION:
XS GIS Cut Line= 3
      1978725.01     13916575.01        1977175.       13915175.
      1976924.99     13914824.99
#Sta/Elev= 30
  2907.7 1569.11  3033.6 1563.14  3207.8 1537.51  3218.4 1534.35  3230.3 1535.97
  3250.5 1534.41  3288.5    1536  3372.6 1531.19  3466.3 1531.65    3511 1529.08
  3630.5 1527.13  4039.4 1523.87    4442 1527.17  4568.4 1526.05    4840 1526.21
  4882.5 1522.87  4923.2 1523.28  4942.1 1517.74  4980.4 1513.38  4986.5 1508.27
  4987.5 1507.77  5036.7 1508.27  5044.8 1511.45  5113.5 1509.24  5184.1 1514.41
  5240.7 1522.77  5278.7 1525.48  5321.3 1527.83  5390.9 1536.84  5426.5 1539.46
#Mann= 9 ,-1 , 0
  2907.7     .07       0  3630.5    .045       0  4568.4    .035       0
  4882.5     .07       0  4923.2      .1       0  4986.5     .05       0
  5036.7      .1       0  5184.1    .035       0  5278.7     .07       0
#XS Ineff= 2 , 0
         4447.31 1527.56
Permanent Ineff=
       F       F
Bank Sta=4986.5,5036.7
XS Rating Curve= 0 ,0
Exp/Cntr=0.3,0.1

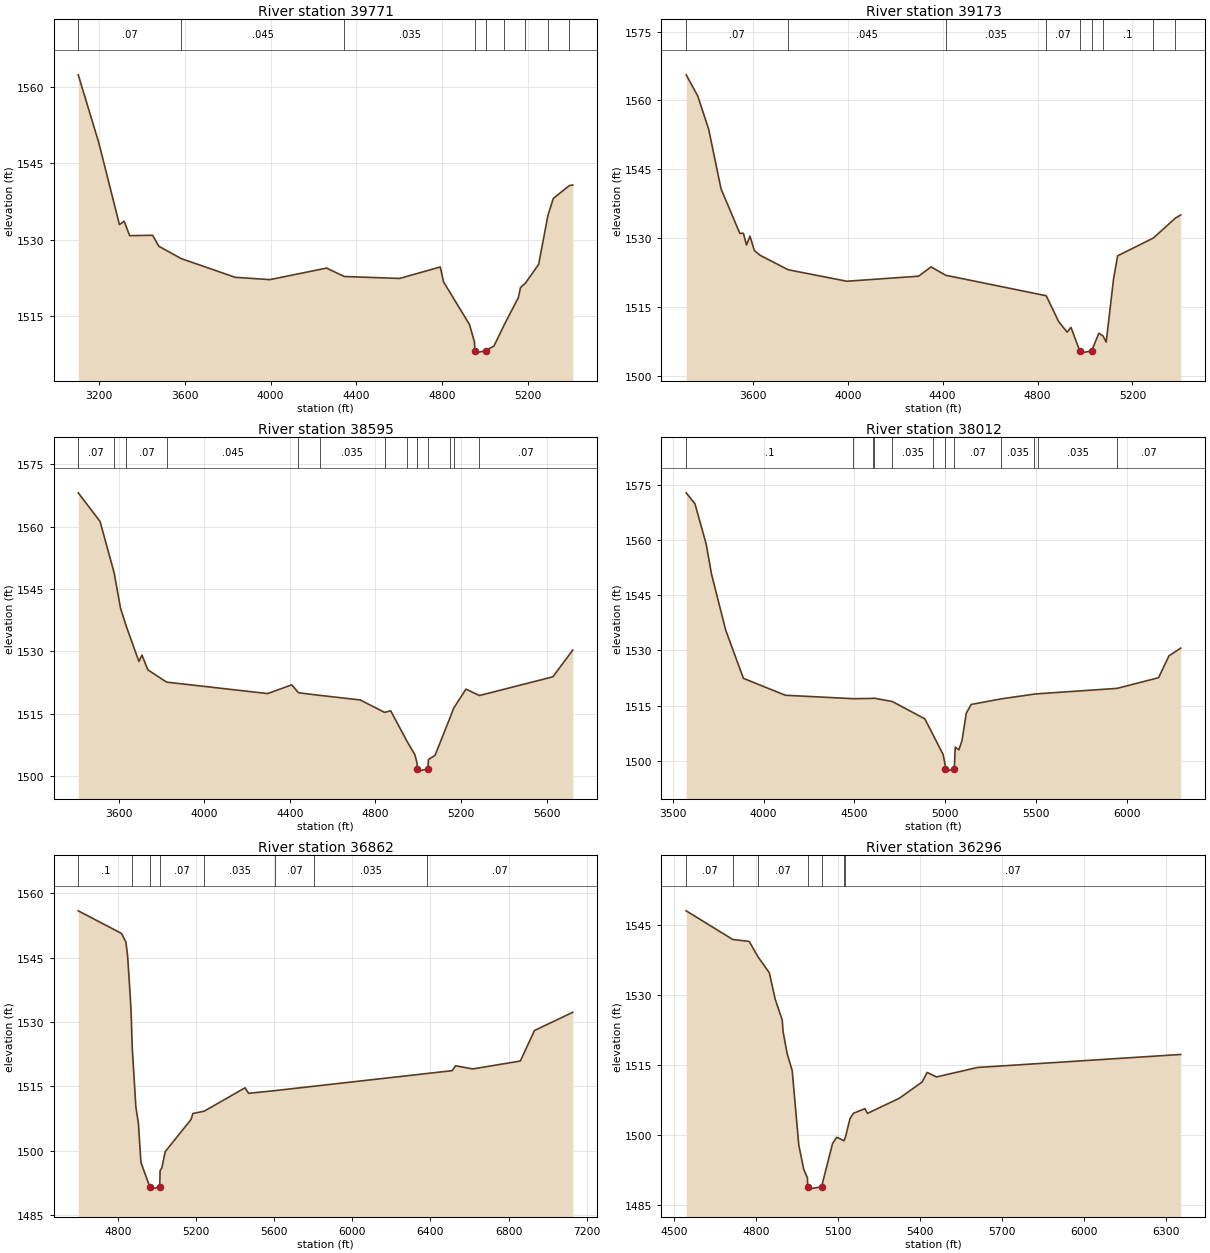
Type RM Length L Ch R = 1 ,39771   ,598,598,598
BEGIN DESCRIPTION:
Cypress Creek 46.0
END DESCRIPTION:
XS GIS Cut Line= 3
      1978674.99     13916474.99        1977575.       13914925.
      1977625.01     13914524.95
#Sta/Elev= 30
  3103.8 1562.33  3199.9 1548.94  3295.6 1532.95  3317.7 1533.61  3343.2 1530.78
  3450.1 1530.86  3479.5 1528.69  3583.7 1526.28  3834.9 1522.61  3997.1 1522.16
  4260.6 1524.42  4343.3 1522.77  4600.9 1522.39  4790.3 1524.64  4805.7 1521.71
  4926.5 1513.35  4949.5 1509.96  4951.7 1508.24  4952.7 1507.74  5001.9 1508.24
  5040.6 1509.14  5088.3 1513.29  5154.6 1518.67  5164.1  1520.6    5187 1521.47
  5248.7 1525.15  5292.1 1534.78    5317 1538.09  5391.9 1540.61  5407.6 1540.72
#Mann= 9 ,-1 , 0
  3103.8     .07       0  3583.7    .045       0  4343.3    .035       0
  4951.7     .05       0  5001.9    .035       0  5088.3     .07       0
    5187    .035       0  5292.1     .07       0  5391.9    .035       0
Bank Sta=4951.7,5001.9
XS Rating Curve= 0 ,0
Exp/Cntr=0.3,0.1

Type RM Length L Ch R = 1 ,39173   ,578,578,578
BEGIN DESCRIPTION:
Cypress Creek 45.0
END DESCRIPTION:
XS GIS Cut Line= 3
      1978825.01     13916475.03        1978175.       13914925.
      1977975.01     13914575.02
#Sta/Elev= 30
  3319.2 1565.57    3368 1560.95    3414 1553.71  3466.1 1540.72  3545.2 1531.04
  3560.4 1531.05  3573.4 1528.49    3588 1530.44  3606.4  1527.3  3630.6 1526.26
  3749.1 1523.11    3996 1520.61  4298.5 1521.71  4351.2 1523.73  4412.9 1521.91
  4836.4 1517.45  4888.8 1511.83  4924.5 1509.52  4940.8 1510.55  4977.7 1505.45
  4978.7 1504.95  5027.9 1505.45  5058.1 1509.27  5075.8  1508.7  5089.2 1507.35
  5120.3 1521.17  5137.5 1526.15    5288 1530.03  5381.1 1534.37  5403.1 1535.05
#Mann= 9 ,-1 , 0
  3319.2     .07       0  3749.1    .045       0  4412.9    .035       0
  4836.4     .07       0  4977.7    .035       0  5027.9     .07       0
  5075.8      .1       0    5288     .07       0  5381.1    .035       0
Bank Sta=4977.7,5027.9
XS Rating Curve= 0 ,0
Exp/Cntr=0.3,0.1

Type RM Length L Ch R = 1 ,38595   ,583,583,583
BEGIN DESCRIPTION:
Cypress Creek 44.0
END DESCRIPTION:
XS GIS Cut Line= 4
      1979074.99     13916474.96        1978725.       13914925.
      1978531.28     13914579.23      1978218.18     13914495.21
#Sta/Elev= 30
  3411.8 1568.17  3513.7 1561.27  3579.5 1548.87    3609 1540.43  3634.9  1536.2
  3695.1 1527.55  3709.3 1529.08  3736.9 1525.53  3824.5 1522.57  4296.4 1519.81
  4408.7 1521.92  4440.3 1520.01  4541.9 1519.37  4728.5 1518.28  4842.6 1515.28
    4871 1515.66  4948.1 1508.24  4983.9 1505.08  4993.9 1503.12  4994.5 1501.63
  4995.5 1501.13  5044.7 1501.63  5047.1 1503.91  5078.1 1504.93  5146.3 1513.78
  5165.1 1516.31  5222.5 1520.89  5285.5 1519.34  5628.3 1523.85  5721.3 1530.29
#Mann= 13 ,-1 , 0
  3411.8     .07       0  3579.5      .1       0  3634.9     .07       0
  3824.5    .045       0  4440.3     .07       0  4541.9    .035       0
  4842.6     .07       0  4948.1    .035       0  4994.5    .035       0
  5044.7    .035       0  5146.3     .07       0  5165.1      .1       0
  5285.5     .07       0
Bank Sta=4994.5,5044.7
XS Rating Curve= 0 ,0
Exp/Cntr=0.3,0.1

Type RM Length L Ch R = 1 ,38012   ,1150,1150,1150
BEGIN DESCRIPTION:
Cypress Creek 43.0
END DESCRIPTION:
XS GIS Cut Line= 4
      1979825.87     13916240.08        1979275.       13914925.
      1979112.33     13914606.94      1978187.27     13914443.06
#Sta/Elev= 30
  3574.3 1572.89  3622.5 1569.92  3684.3 1558.97  3713.6 1550.81  3791.7 1535.55
  3889.3 1522.42  4120.2 1517.82  4492.8 1516.89  4600.8 1516.96  4606.7 1517.05
  4708.9 1516.12  4887.8 1511.42    4935 1506.91  4988.6 1501.72  5000.1 1498.88
  5000.2 1497.68  5001.2 1497.18  5050.4 1497.68  5055.6 1503.69  5075.8 1502.99
  5092.7 1505.46  5116.3 1512.93  5143.2 1515.32  5309.3 1516.84  5490.5 1518.13
  5512.7 1518.23  5946.4 1519.69  6174.9 1522.59  6232.1 1528.54  6296.8 1530.64
#Mann= 12 ,-1 , 0
  3574.3      .1       0  4492.8     .07       0  4600.8    .035       0
  4606.7     .07       0  4708.9    .035       0    4935     .07       0
  5000.2     .05       0  5050.4     .07       0  5309.3    .035       0
  5490.5     .07       0  5512.7    .035       0  5946.4     .07       0
Bank Sta=5000.2,5050.4
XS Rating Curve= 0 ,0
Exp/Cntr=0.3,0.1

Type RM Length L Ch R = 1 ,36862   ,566,566,566
BEGIN DESCRIPTION:
Cypress Creek 42.0
END DESCRIPTION:
XS GIS Cut Line= 3
      1980374.98     13914824.96        1980175.       13914475.
      1978048.86     13914366.11
#Sta/Elev= 30
  4596.6 1555.91  4818.2 1550.64  4840.5 1548.66  4849.3  1545.4  4863.1 1535.72
  4867.4 1532.02  4873.1 1523.91  4891.6  1510.2  4904.6 1506.37  4917.4 1497.31
  4963.1 1491.57  4964.1 1491.07  5013.6 1491.57  5015.7  1495.4  5024.3 1496.02
  5042.1 1499.82  5174.3 1507.32  5183.3 1508.69  5241.1 1509.22  5450.7 1514.68
  5468.7 1513.39  5606.1 1514.03  5804.5 1515.05  6384.3 1518.02    6511 1518.67
  6529.1 1519.81  6616.2 1519.07  6860.3 1520.92  6932.6 1528.03  7128.6 1532.27
#Mann= 8 ,-1 , 0
  4596.6      .1       0  4873.1     .07       0  4963.1     .05       0
  5013.6     .07       0  5241.1    .035       0  5606.1     .07       0
  5804.5    .035       0  6384.3     .07       0
Bank Sta=4963.1,5013.6
XS Rating Curve= 0 ,0
Exp/Cntr=0.3,0.1

Type RM Length L Ch R = 1 ,36296   ,704,704,704
BEGIN DESCRIPTION:
Cypress Creek 41.0
END DESCRIPTION:
XS GIS Cut Line= 4
      1980525.01     13914225.01      1980324.41     13913936.49
        1980225.       13913925.      1978919.19     13914291.34
#Sta/Elev= 30
  4544.4 1547.96  4714.5 1541.84  4774.9 1541.42  4806.3 1538.18  4848.2 1534.74
  4869.7 1529.09  4895.5 1524.61  4898.6 1522.14  4913.7  1517.4  4931.9 1513.82
    4956  1497.9  4974.1  1492.7  4987.6  1490.9  4988.6 1488.98  4989.6 1488.48
  5039.2 1488.98  5079.4 1498.23    5095 1499.57  5121.2 1498.81  5126.6 1499.62
  5143.5  1503.6  5155.9 1504.69  5197.8 1505.68  5207.1 1504.67  5323.5  1507.9
  5406.5 1511.36  5425.2 1513.42  5459.5 1512.46  5609.1 1514.48  6352.1 1517.26
#Mann= 7 ,-1 , 0
  4544.4     .07       0  4714.5      .1       0  4806.3     .07       0
  4988.6     .05       0  5039.2     .07       0  5121.2      .1       0
  5126.6     .07       0
Bank Sta=4988.6,5039.2
XS Rating Curve= 0 ,0
Exp/Cntr=0.3,0.1