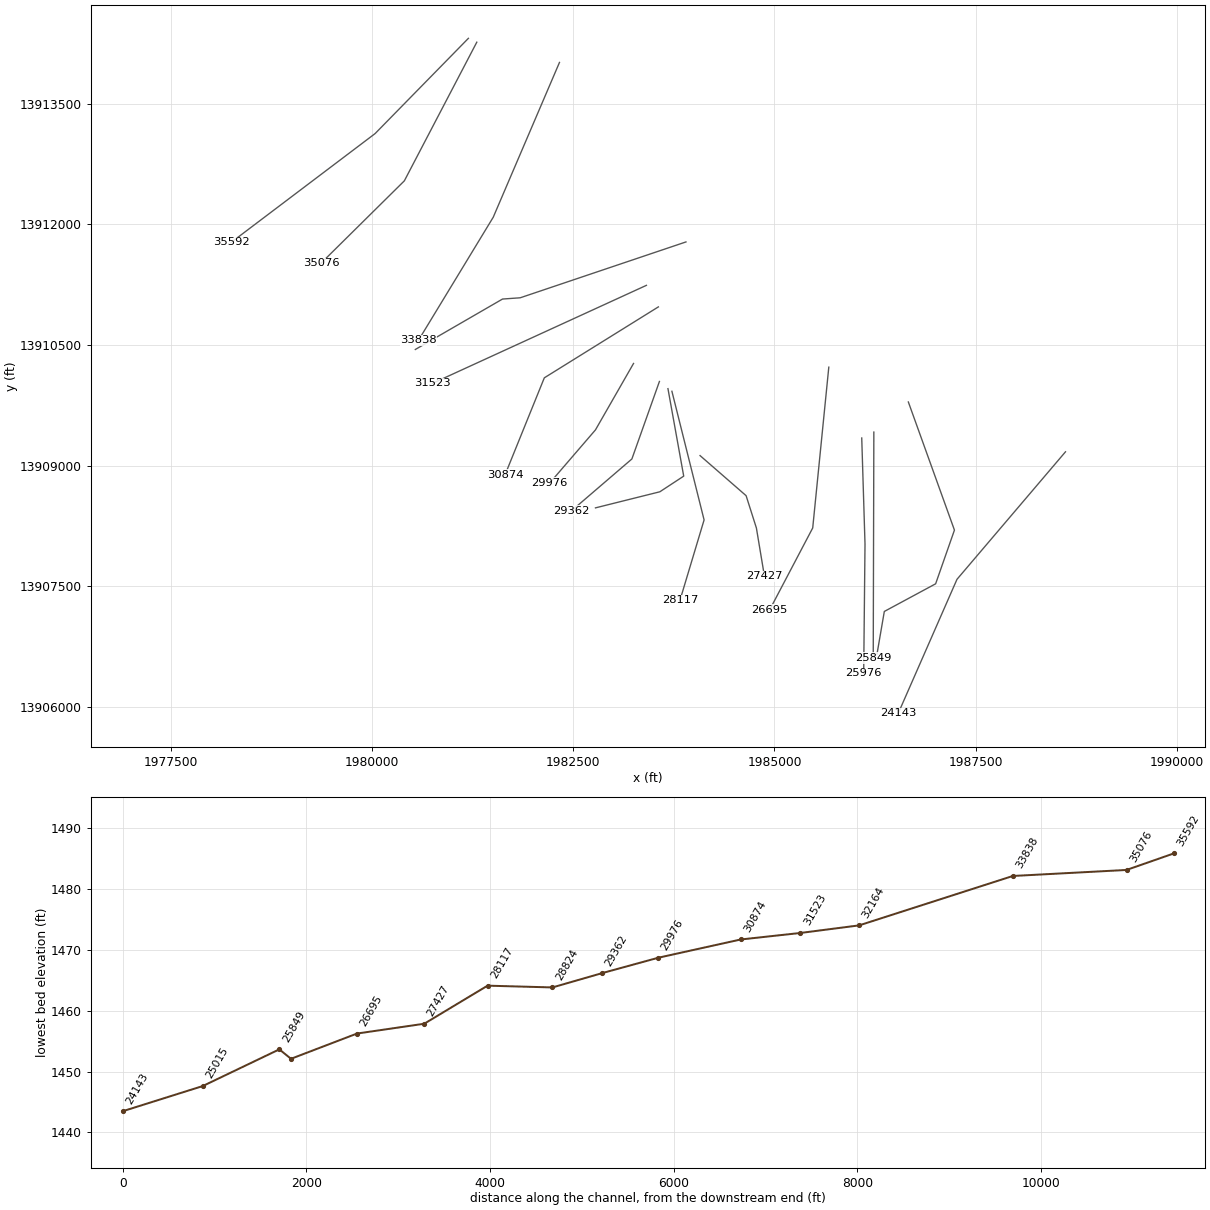
HEC-RAS study Cypress Creek.prj: Cypress Creek Base Level Engineering

--- Cypress Creek.g01 (geometry) --- (continued)

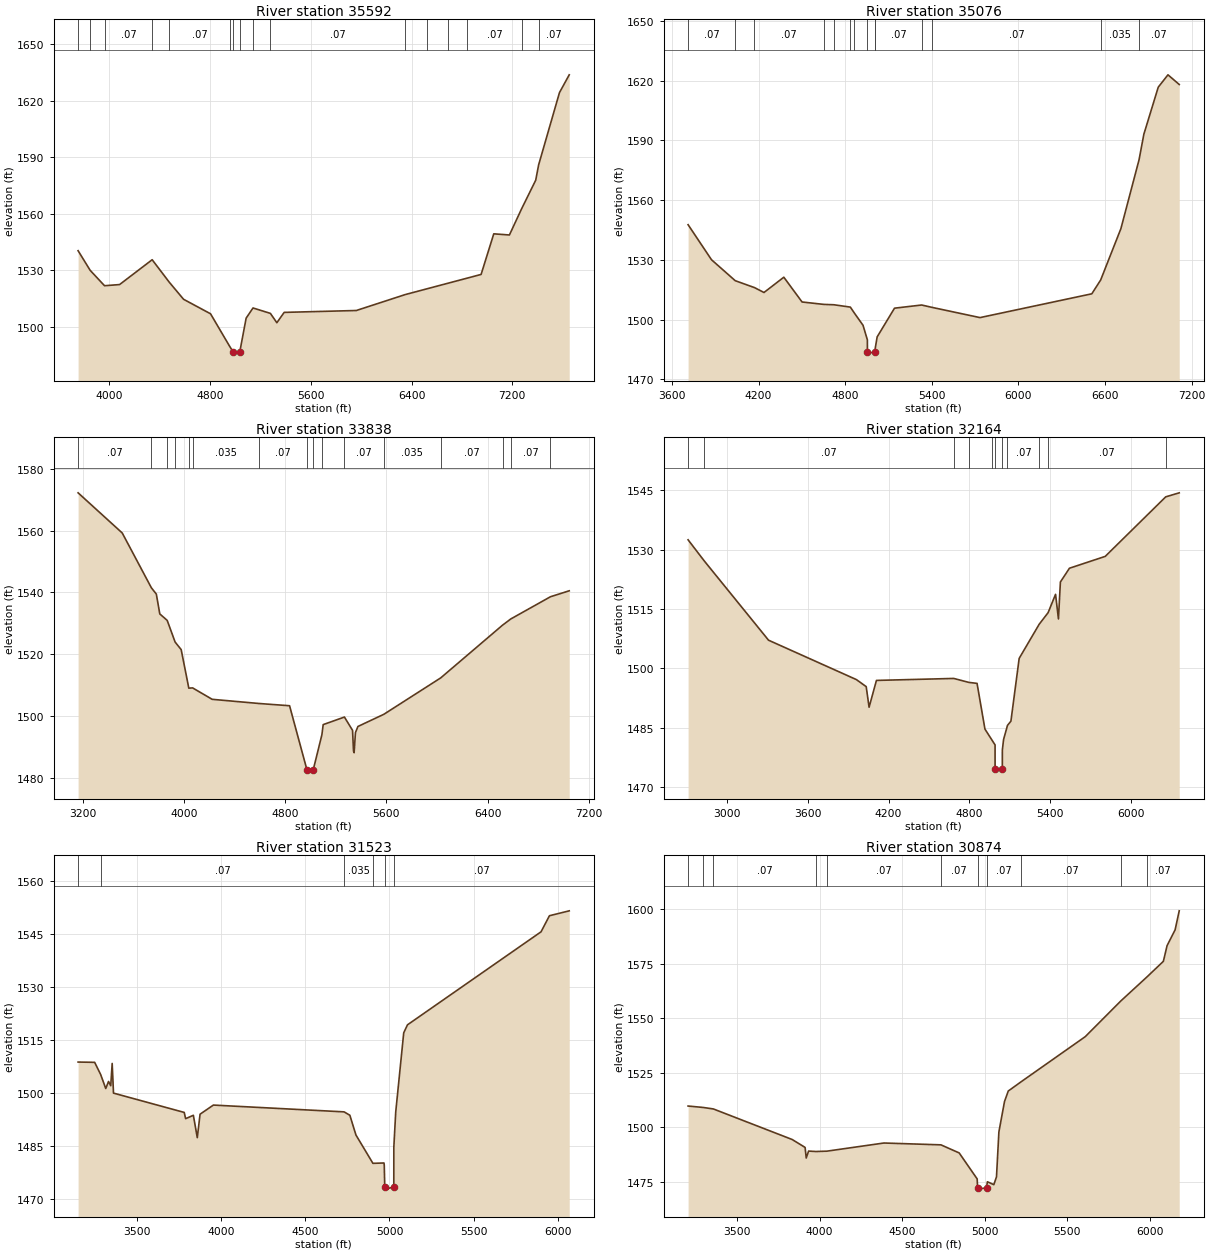
Type RM Length L Ch R = 1 ,35592   ,516,516,516
BEGIN DESCRIPTION:
Cypress Creek 40.4
END DESCRIPTION:
XS GIS Cut Line= 3
      1981195.69     13914314.41      1980036.16     13913129.93
      1978246.31     13911776.02
#Sta/Elev= 30
    3751 1540.31  3846.9 1529.87  3960.9 1521.69  4080.5  1522.3  4339.5 1535.51
  4475.1 1523.58  4588.8 1514.48  4803.2 1506.77  4955.8 1489.38  4984.4 1486.35
  4985.4 1485.85    5035 1486.35    5086 1504.44  5140.6 1509.86  5278.5 1506.99
    5330 1502.01  5388.1 1507.51  5961.1 1508.51  6349.3 1516.97  6520.3 1520.01
  6685.9 1522.95  6843.1 1525.74  6952.6 1527.69  7053.3 1549.28  7177.5 1548.66
  7274.7 1562.62  7386.6  1577.8  7409.7 1585.94  7575.4 1624.39  7652.8 1633.82
#Mann= 16 ,-1 , 0
    3751     .07       0  3846.9      .1       0  3960.9     .07       0
  4339.5    .035       0  4475.1     .07       0  4955.8      .1       0
  4984.4     .05       0    5035      .1       0  5140.6    .035       0
  5278.5     .07       0  6349.3    .035       0  6520.3     .07       0
  6685.9    .035       0  6843.1     .07       0  7274.7    .035       0
  7409.7     .07       0
Bank Sta=4984.4,5035
XS Rating Curve= 0 ,0
Exp/Cntr=0.3,0.1

Type RM Length L Ch R = 1 ,35076   ,1238,1238,1238
BEGIN DESCRIPTION:
Cypress Creek 40.3
END DESCRIPTION:
XS GIS Cut Line= 3
      1981299.94     13914266.34      1980399.57     13912542.15
      1979364.09     13911517.74
#Sta/Elev= 30
    3712 1547.62  3874.2 1530.02  4038.6  1519.5  4171.8 1516.04  4237.7 1513.58
  4375.1 1521.25  4501.4 1508.81  4650.4 1507.61    4723 1507.41  4835.8 1506.24
  4864.2  1503.2  4923.8 1497.09  4953.8 1489.78  4954.1 1483.63  4955.1 1483.13
  5004.7 1483.63  5009.9 1486.28  5021.6 1491.29  5141.7  1505.7  5329.7 1507.29
  5404.8 1506.05  5733.9 1500.97  6508.2 1512.92  6569.5 1519.84  6709.7 1545.64
  6835.6 1580.27  6868.8 1593.08  6968.5 1616.69  7035.7 1622.88  7113.7 1618.04
#Mann= 14 ,-1 , 0
    3712     .07       0  4038.6      .1       0  4171.8     .07       0
  4650.4    .035       0    4723      .1       0  4835.8     .07       0
  4864.2      .1       0  4954.1     .05       0  5004.7      .1       0
  5009.9     .07       0  5329.7    .035       0  5404.8     .07       0
  6569.5    .035       0  6835.6     .07       0
Bank Sta=4954.1,5004.7
XS Rating Curve= 0 ,0
Exp/Cntr=0.3,0.1

Type RM Length L Ch R = 1 ,33838   ,1674,1674,1674
BEGIN DESCRIPTION:
Cypress Creek 40.2
END DESCRIPTION:
XS GIS Cut Line= 3
      1982327.57     13914014.62      1981504.41     13912089.64
      1980575.37     13910559.49
#Sta/Elev= 30
  3161.8 1572.25    3511 1559.24  3741.3  1541.5  3780.4 1539.47  3807.9 1533.04
  3866.3 1530.95  3928.9 1523.94    3977 1521.48  4037.3 1509.01  4067.2 1509.09
  4222.2 1505.39  4592.1 1504.04    4834 1503.31  4970.9 1482.64  4971.9 1482.14
  5021.7 1482.64  5089.6 1493.91  5099.9  1497.2  5267.9 1499.65  5332.1 1495.34
  5339.7 1488.63  5344.4 1488.11    5355 1494.61  5374.7  1496.6  5579.9 1500.55
    6029 1512.32  6518.4 1529.41  6583.4 1531.41    6897  1538.6  7045.5 1540.53
#Mann= 16 ,-1 , 0
  3161.8     .07       0  3741.3      .1       0  3866.3     .07       0
  3928.9      .1       0  4037.3     .07       0  4067.2    .035       0
  4592.1     .07       0  4970.9     .05       0  5021.7     .07       0
  5089.6    .035       0  5267.9     .07       0  5579.9    .035       0
    6029     .07       0  6518.4    .035       0  6583.4     .07       0
    6897    .035       0
Bank Sta=4970.9,5021.7
XS Rating Curve= 0 ,0
Exp/Cntr=0.3,0.1

Type RM Length L Ch R = 1 ,32164   ,641,641,641
BEGIN DESCRIPTION:
Cypress Creek 40.1
END DESCRIPTION:
XS GIS Cut Line= 4
      1983899.73     13911782.32       1981839.8     13911087.76
      1981619.79     13911072.09      1980536.04     13910444.88
#Sta/Elev= 30
  2711.6 1532.52  2831.6 1527.18    3309 1507.13  3961.2 1497.17    4034 1495.39
  4055.5 1490.18    4110 1496.96  4684.1 1497.46  4796.1 1496.46  4857.1 1496.21
  4915.7 1484.65    4969 1481.81  4990.9 1480.65    4991 1474.62  4992.1 1474.02
  5044.8 1474.62    5045 1479.37    5054 1482.02  5083.1 1485.59  5108.5 1486.65
  5169.8 1502.53    5318 1511.14  5384.8  1514.1  5439.9 1518.73  5461.5 1512.51
  5475.9 1521.85  5543.1 1525.33  5808.9 1528.33  6257.9 1543.38  6358.2  1544.4
#Mann= 11 ,-1 , 0
  2711.6      .1       0  2831.6     .07       0  4684.1    .035       0
  4796.1     .07       0    4969      .1       0    4991     .05       0
  5044.8      .1       0  5083.1     .07       0    5318    .035       0
  5384.8     .07       0  6257.9    .035       0
Bank Sta=4991,5044.8
XS Rating Curve= 0 ,0
Exp/Cntr=0.3,0.1

Type RM Length L Ch R = 1 ,31523   ,649,649,649
BEGIN DESCRIPTION:
Cypress Creek 40.0
END DESCRIPTION:
XS GIS Cut Line= 2
      1983408.13     13911242.51      1980752.52       13910025.
#Sta/Elev= 30
    3148 1508.69  3246.5 1508.61  3282.4 1505.15  3312.5 1501.21    3329  1503.2
  3342.2    1502  3350.7  1508.3  3358.6 1499.91  3779.3 1494.45  3787.6 1492.69
  3833.6 1493.64    3857 1487.32  3873.5 1493.95  3952.7 1496.53  4730.3 1494.61
  4764.5 1493.65  4800.8 1488.06  4901.7 1480.06  4967.3 1480.16  4969.1 1479.59
  4972.1 1473.37  4973.2 1472.77  5025.9 1473.37  5026.1 1484.67  5037.4  1494.6
  5084.9 1516.95  5107.2 1519.21  5901.8 1545.51  5951.6 1550.05  6069.4 1551.44
#Mann= 6 ,-1 , 0
    3148      .1       0  3282.4     .07       0  4730.3    .035       0
  4901.7     .07       0  4972.1     .05       0  5025.9     .07       0
Bank Sta=4972.1,5025.9
XS Rating Curve= 0 ,0
Exp/Cntr=0.3,0.1

Type RM Length L Ch R = 1 ,30874   ,898,898,898
BEGIN DESCRIPTION:
Cypress Creek 39.0
END DESCRIPTION:
XS GIS Cut Line= 3
      1983556.84     13910974.51      1982139.24     13910092.23
       1981650.8     13908884.93
#Sta/Elev= 30
  3204.5 1509.76  3295.5 1509.11  3357.6 1508.42  3834.4 1494.43  3912.6  1490.8
  3919.4 1485.95  3933.8 1489.13  3977.2 1488.93  4044.6 1489.09  4389.6 1492.82
  4734.5 1491.98    4845 1488.28  4953.9 1476.37  4956.4  1472.3  4957.6  1471.7
  5010.4  1472.3  5015.8 1475.07  5054.6 1473.74  5070.8 1477.32  5085.3 1497.89
  5119.3 1511.82    5142 1516.63  5219.2 1520.84    5608 1541.54  5822.3 1557.82
  5981.6 1568.91  6080.6 1576.04  6103.1 1583.23  6151.7 1590.46  6176.6 1599.17
#Mann= 11 ,-1 , 0
  3204.5     .07       0  3295.5      .1       0  3357.6     .07       0
  3977.2    .035       0  4044.6     .07       0  4734.5     .07       0
  4956.4     .05       0  5010.4     .07       0  5219.2     .07       0
  5822.3    .035       0  5981.6     .07       0
Bank Sta=4956.4,5010.4
XS Rating Curve= 0 ,0
Exp/Cntr=0.3,0.1

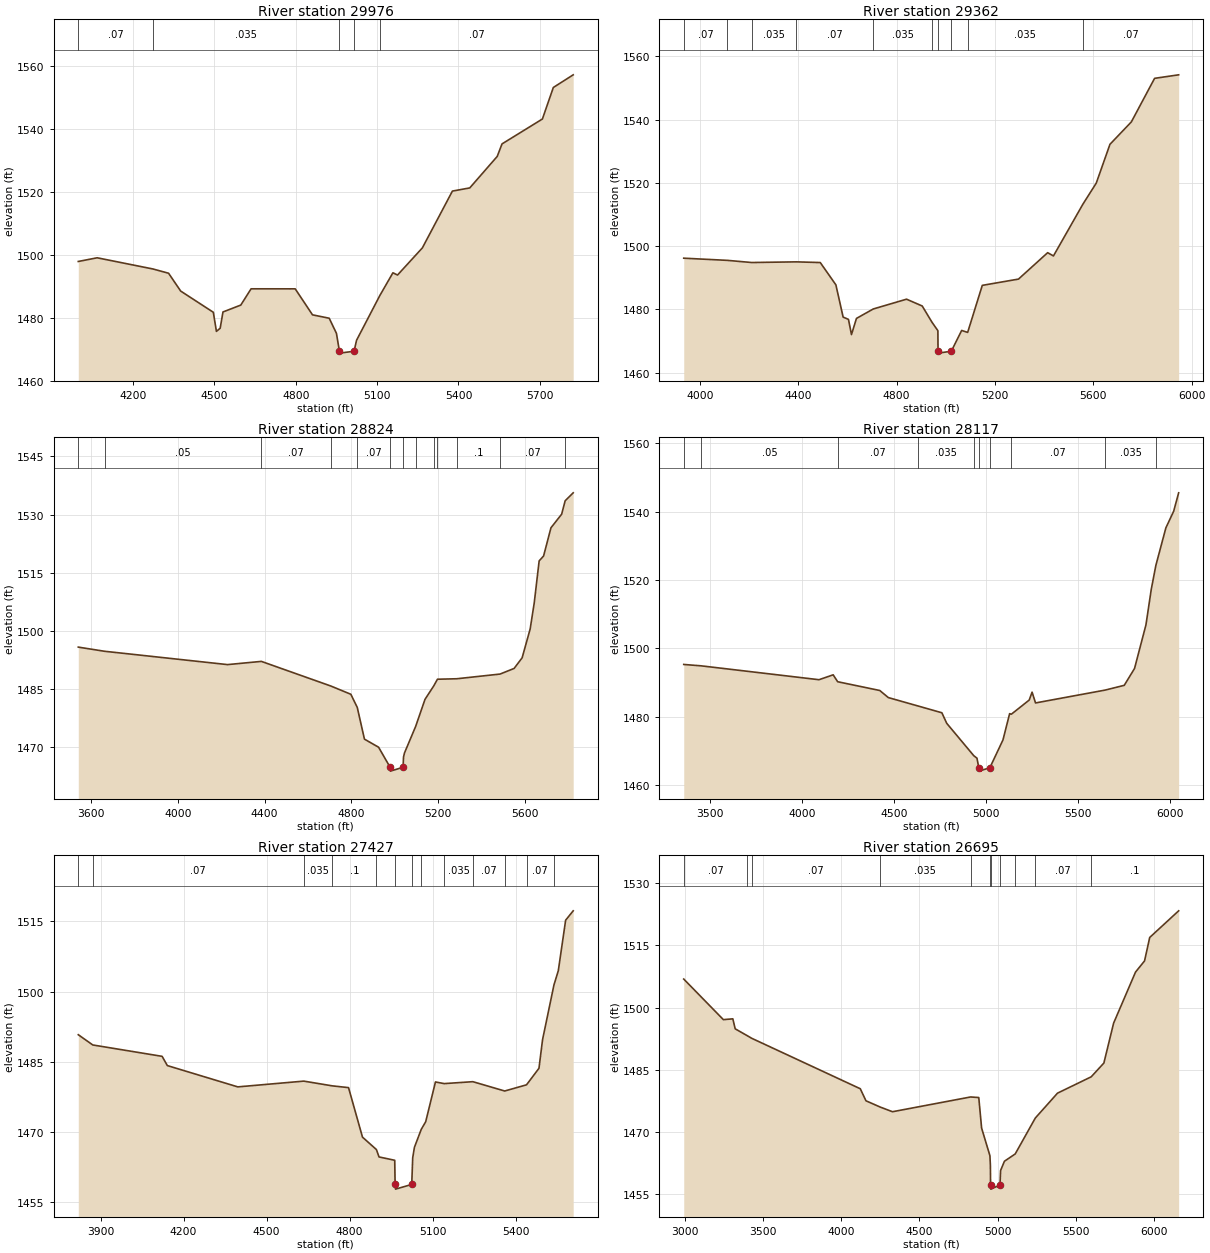
Type RM Length L Ch R = 1 ,29976   ,614,614,614
BEGIN DESCRIPTION:
Cypress Creek 38.0
END DESCRIPTION:
XS GIS Cut Line= 3
      1983248.04     13910270.85      1982775.13     13909445.06
       1982206.1     13908783.53
#Sta/Elev= 30
  3998.6 1497.83  4068.3    1499    4274 1495.44  4331.4 1494.09  4376.1 1488.42
  4496.4 1481.68  4507.7 1475.61  4521.6 1476.61  4531.9 1481.78  4597.6 1483.97
  4635.5 1489.14  4798.2 1489.13  4861.9 1480.87  4923.5 1479.79  4950.2 1474.98
  4961.1  1469.3  4962.2  1468.7  5015.1  1469.3  5024.3 1472.79  5109.8 1486.96
  5158.3 1494.23  5175.3 1493.52  5266.8 1502.14  5377.6  1520.2  5441.6 1521.21
  5542.8 1531.22  5560.4 1535.19  5709.3 1543.11  5749.6 1553.13  5822.8 1557.15
#Mann= 5 ,-1 , 0
  3998.6     .07       0    4274    .035       0  4961.1     .05       0
  5015.1    .035       0  5109.8     .07       0
Bank Sta=4961.1,5015.1
XS Rating Curve= 0 ,0
Exp/Cntr=0.3,0.1

Type RM Length L Ch R = 1 ,29362   ,538,538,538
BEGIN DESCRIPTION:
Cypress Creek 37.0
END DESCRIPTION:
XS GIS Cut Line= 3
      1983569.85     13910046.99      1983227.63     13909083.09
      1982476.43     13908438.02
#Sta/Elev= 30
  3934.2 1496.17    4112 1495.48  4210.6  1494.8  4392.3 1495.01  4489.5 1494.79
    4553 1487.75  4582.5 1477.55  4604.2 1476.82  4616.4 1472.02  4636.7 1477.13
  4705.2 1480.12  4840.4 1483.21  4904.1 1481.06  4943.8 1475.94  4967.9 1473.25
  4968.5 1466.76  4969.6 1466.16  5022.5 1466.76  5064.6 1473.33    5089 1472.71
  5148.5 1487.58  5295.7 1489.56  5414.4 1497.91  5437.9 1496.88  5557.8 1513.25
  5612.1 1519.91  5667.8 1532.17  5754.8 1539.25  5849.3 1553.02  5947.2 1554.13
#Mann= 10 ,-1 , 0
  3934.2     .07       0    4112     .05       0  4210.6    .035       0
  4392.3     .07       0  4705.2    .035       0  4943.8     .07       0
  4968.5     .05       0  5022.5     .07       0    5089    .035       0
  5557.8     .07       0
Bank Sta=4968.5,5022.5
XS Rating Curve= 0 ,0
Exp/Cntr=0.3,0.1

Type RM Length L Ch R = 1 ,28824   ,707,707,707
BEGIN DESCRIPTION:
Cypress Creek 36.0
END DESCRIPTION:
XS GIS Cut Line= 4
      1983675.91      13909957.7      1983871.77     13908869.76
        1983575.       13908675.      1982775.02     13908475.01
#Sta/Elev= 30
  3539.6  1495.8  3660.7 1494.73  4228.8 1491.29  4384.8 1492.12    4705 1485.78
    4798 1483.64  4827.7 1480.24  4860.8 1472.07  4926.2 1469.98  4979.3 1464.82
  4980.8 1463.82  5039.3 1464.82  5041.1 1467.44  5045.8 1468.52  5097.1 1475.33
  5140.4 1482.33  5180.8  1485.8  5197.9 1487.52    5287 1487.64  5486.9 1488.85
  5551.8  1490.3  5588.9 1493.05    5626  1500.5  5644.6 1507.15  5667.4 1518.03
  5687.9  1519.3  5721.9 1526.57  5771.3 1530.08  5787.5 1533.54  5824.6 1535.59
#Mann= 13 ,-1 , 0
  3539.6     .07       0  3660.7     .05       0  4384.8     .07       0
    4705    .035       0  4827.7     .07       0  4979.3     .05       0
  5039.3     .07       0  5097.1    .035       0  5180.8      .1       0
  5197.9    .035       0    5287      .1       0  5486.9     .07       0
  5787.5    .035       0
Bank Sta=4979.3,5039.3
XS Rating Curve= 0 ,0
Exp/Cntr=0.3,0.1

Type RM Length L Ch R = 1 ,28117   ,690,690,690
BEGIN DESCRIPTION:
Cypress Creek 35.0
END DESCRIPTION:
XS GIS Cut Line= 3
      1983725.01     13909924.97        1984125.       13908325.
      1983825.01     13907325.04
#Sta/Elev= 30
  3356.5 1495.29  3450.5 1494.89  4092.4 1490.83  4169.7 1492.26  4194.2 1490.24
  4423.3 1487.68  4469.7 1485.61  4630.8 1483.16  4761.1 1481.17  4787.7 1478.08
    4935 1468.61  4952.1  1467.9  4962.2 1465.11  4963.7 1464.11  5022.3 1465.11
  5093.5 1473.21  5129.9 1480.91  5139.4 1480.75  5236.4 1484.88  5252.1  1487.2
  5270.9 1484.04  5649.9  1487.8  5753.6 1489.19  5809.6 1494.11  5871.7 1506.86
  5900.6 1517.23  5925.7 1524.25  5980.1 1535.21  6022.6 1540.08  6049.7 1545.46
#Mann= 10 ,-1 , 0
  3356.5     .07       0  3450.5     .05       0  4194.2     .07       0
  4630.8    .035       0    4935      .1       0  4962.2     .05       0
  5022.3      .1       0  5139.4     .07       0  5649.9    .035       0
  5925.7      .1       0
Bank Sta=4962.2,5022.3
XS Rating Curve= 0 ,0
Exp/Cntr=0.3,0.1

Type RM Length L Ch R = 1 ,27427   ,732,732,732
BEGIN DESCRIPTION:
Cypress Creek 34.0
END DESCRIPTION:
XS GIS Cut Line= 4
      1984074.99     13909125.01      1984647.23     13908626.63
        1984775.       13908225.        1984875.     13907624.98
#Sta/Elev= 30
  3819.6 1490.82    3872 1488.63  4122.6  1486.2  4141.4 1484.23    4396 1479.68
  4634.7 1480.91  4737.4  1479.9  4796.3 1479.52  4846.7 1468.95    4897  1466.3
  4906.5 1464.72  4963.2 1464.01  4964.6 1458.85  4966.1 1457.85  5024.7 1458.85
  5028.2 1464.54  5034.4 1466.77    5059  1470.6  5075.2 1472.25  5110.4 1480.73
  5141.9 1480.38  5245.5 1480.79  5360.7  1478.8  5439.5 1480.12  5484.5 1483.65
  5497.5 1489.77  5538.7 1501.46  5554.4 1504.49  5580.9 1515.27  5608.2 1517.27
#Mann= 13 ,-1 , 0
  3819.6     .05       0    3872     .07       0  4634.7    .035       0
  4737.4      .1       0    4897    .035       0  4964.6    .035       0
  5024.7    .035       0    5059      .1       0  5141.9    .035       0
  5245.5     .07       0  5360.7    .035       0  5439.5     .07       0
  5538.7      .1       0
Bank Sta=4964.6,5024.7
XS Rating Curve= 0 ,0
Exp/Cntr=0.3,0.1

Type RM Length L Ch R = 1 ,26695   ,719,719,719
BEGIN DESCRIPTION:
Cypress Creek 33.0
END DESCRIPTION:
XS GIS Cut Line= 3
        1985675.     13910224.98        1985475.       13908225.
      1984939.72      13907206.1
#Sta/Elev= 30
  2994.5 1506.89  3247.7  1497.1    3308  1497.3  3323.1 1494.89  3400.7 1493.22
  3427.9 1492.62  4122.1 1480.44  4158.2 1477.54  4247.1 1476.06  4327.7  1474.9
  4826.8 1478.46  4878.8 1478.32  4896.9 1470.96  4949.9 1464.31    4953    1462
  4954.2 1457.24  4955.7 1456.24  5014.4 1457.24    5018 1460.72  5042.8 1462.97
  5111.5 1464.72  5239.9 1473.38  5381.7 1479.38  5596.9 1483.32  5677.8 1486.64
    5740 1496.26  5879.9 1508.57  5937.5 1511.26  5970.6 1516.92  6155.4 1523.34
#Mann= 11 ,-1 , 0
  2994.5     .07       0  3400.7    .035       0  3427.9     .07       0
  4247.1    .035       0  4826.8     .07       0    4953    .035       0
  4954.2    .035       0  5014.4    .035       0  5111.5      .1       0
  5239.9     .07       0  5596.9      .1       0
Bank Sta=4954.2,5014.4
XS Rating Curve= 0 ,0
Exp/Cntr=0.3,0.1

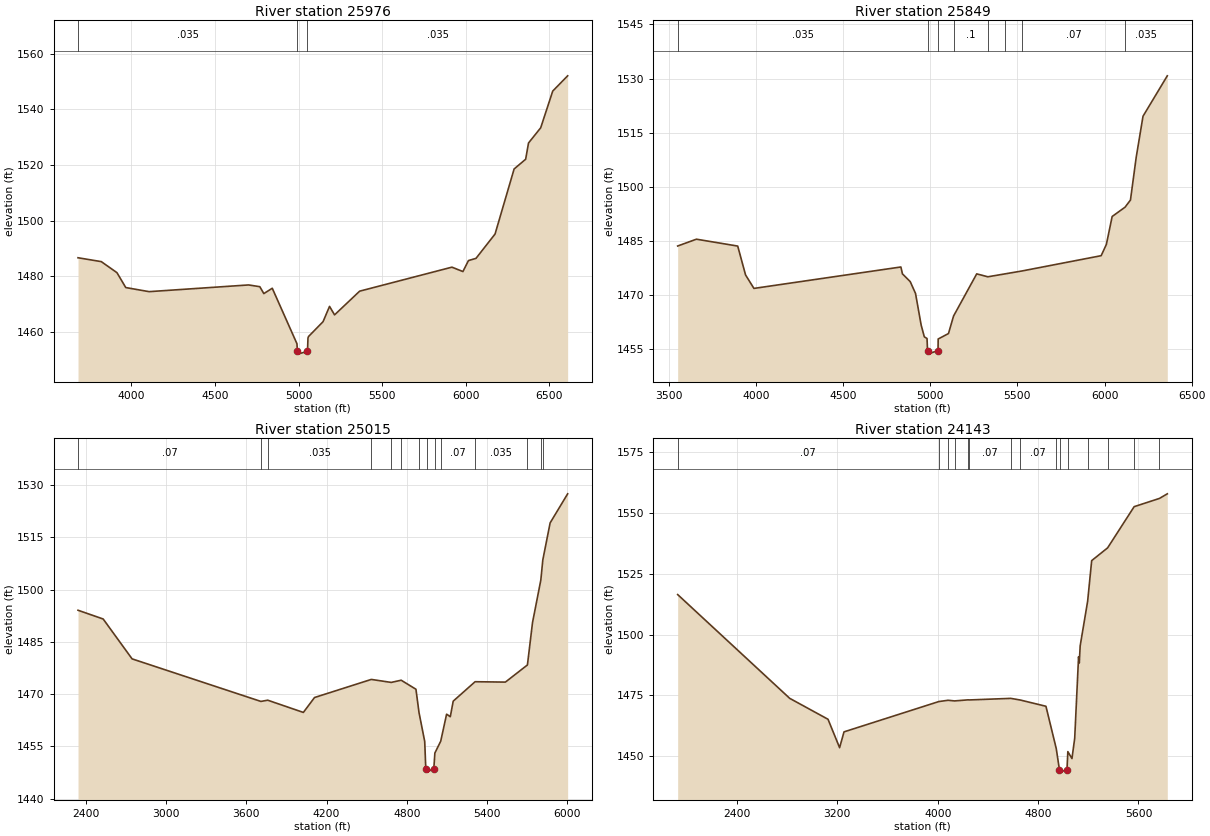
Type RM Length L Ch R = 1 ,25976   ,127,127,127
BEGIN DESCRIPTION:
Cypress Creek 32.0
END DESCRIPTION:
XS GIS Cut Line= 3
      1986084.35     13909344.01        1986125.       13908025.
      1986108.53     13906415.82
#Sta/Elev= 30
  3680.4 1486.72  3819.5 1485.33  3913.3 1481.36    3966 1476.01  4105.4 1474.54
  4700.8 1476.95  4767.9 1476.32  4791.9 1473.84  4842.4 1475.76    4990 1455.83
  4992.9 1453.09  4994.4 1452.09  5053.1 1453.09    5056 1457.86    5059  1458.4
  5146.2 1463.75    5185 1469.25    5215 1466.19    5365 1474.71  5917.1 1483.34
  5982.8 1481.76    6016 1485.71  6061.1  1486.5  6175.1 1495.25  6289.1 1518.62
  6358.1 1522.12  6375.3 1527.96  6448.1 1533.42  6520.1 1546.61  6609.3 1552.09
#Mann= 3 ,-1 , 0
  3680.4    .035       0  4992.9    .035       0  5053.1    .035       0
Bank Sta=4992.9,5053.1
XS Rating Curve= 0 ,0
Exp/Cntr=0.3,0.1

Type RM Length L Ch R = 1 ,25849   ,834,834,834
BEGIN DESCRIPTION:
Cypress Creek 31.5
END DESCRIPTION:
XS GIS Cut Line= 2
      1986234.85     13909417.54      1986227.26     13906608.75
#Sta/Elev= 30
  3551.4  1483.6  3658.9 1485.49  3895.9 1483.58  3940.9 1475.58  3988.9 1471.85
  4831.9 1477.79  4840.9 1475.88  4885.5 1473.73  4915.9 1470.46  4948.3 1461.67
  4966.3 1458.44  4981.9 1457.97  4984.8 1454.64  4986.3 1453.64    5045 1454.64
  5045.8 1457.83  5104.9 1459.34  5134.1  1464.2  5266.9 1475.88  5330.9 1475.07
  5429.3 1475.88  5527.6 1476.69  5980.9 1480.92  6010.9 1484.07  6043.9 1491.78
  6117.9 1494.36  6148.9 1496.34  6181.9  1508.2  6220.9 1519.56  6360.2 1530.76
#Mann= 8 ,-1 , 0
  3551.4    .035       0  4984.8    .035       0    5045    .035       0
  5134.1      .1       0  5330.9     .07       0  5429.3    .035       0
  5527.6     .07       0  6117.9    .035       0
Bank Sta=4984.8,5045
XS Rating Curve= 0 ,0
Exp/Cntr=0.3,0.1

Type RM Length L Ch R = 1 ,25015   ,872,872,872
BEGIN DESCRIPTION:
Cypress Creek 31.4
END DESCRIPTION:
XS GIS Cut Line= 5
      1986663.59     13909792.06       1987236.5     13908198.35
      1987002.79     13907530.71      1986364.97     13907186.79
      1986273.85     13906655.81
#Sta/Elev= 30
  2339.9 1494.09  2528.1 1491.58  2744.5 1480.13  3708.41467.913  3759.71468.263
  4026.4 1464.75  4109.8 1469.03  4534.71474.228  4683.81473.369  4758.3    1474
  4868.9 1471.41  4891.9 1464.71  4934.5 1456.42  4942.6 1448.61  4944.1 1447.61
  4950.3 1447.61  5002.8 1448.61  5010.51453.086  5054.3 1456.49  5098.3 1464.25
  5125.9 1463.52  5147.8 1467.99  5311.6 1473.57  5538.3 1473.46  5703.2 1478.38
  5741.2 1490.53  5803.5 1502.77  5818.4 1508.56  5873.1 1519.17  6004.2 1527.52
#Mann= 14 ,-1 , 0
  2339.9     .07       0  3708.4     .07       0  3759.7    .035       0
  4534.7     .07       0  4683.8    .035       0  4758.3     .07       0
  4891.9      .1       0  4950.3     .05       0  5010.5      .1       0
  5054.3     .07       0  5311.6    .035       0  5703.2     .07       0
  5803.5      .1       0  5818.4    .035       0
#Block Obstruct= 2 , 0
         4522.73  1474.7
Bank Sta=4942.6,5002.8
XS Rating Curve= 0 ,0
Exp/Cntr=0.3,0.1

Type RM Length L Ch R = 1 ,24143   ,805,805,805
BEGIN DESCRIPTION:
Mapping XS 7aa464f1
END DESCRIPTION:
XS GIS Cut Line= 3
      1988616.68     13909172.27      1987268.13     13907586.34
       1986537.7      13905919.2
#Sta/Elev= 30
  1927.7 1516.46  2820.6  1473.8  3125.9  1465.2  3218.2 1453.52  3253.3 1460.02
  4009.5 1472.49  4082.71472.998  4133.9 1472.74  4242.81473.182  4250.7 1473.14
  4582.2 1473.79  4657.9 1473.11  4862.5 1470.54  4944.61453.178  4970.1 1444.47
  4971.6 1443.47  4976.7 1443.47  5030.4 1444.47    50371451.905  5069.9 1449.05
  5091.8 1457.41  5122.6 1490.91  5128.1 1488.31  5135.4 1495.39  5194.8 1513.71
    5227 1530.41  5354.1 1535.66  5565.5 1552.59  5767.2 1555.98  5829.6 1557.87
#Mann= 15 ,-1 , 0
  1927.7     .07       0  4009.5     .07       0  4082.7    .035       0
  4133.9     .07       0  4242.8    .035       0  4250.7     .07       0
  4582.2    .035       0  4657.9     .07       0  4944.6      .1       0
  4976.7     .05       0    5037      .1       0  5194.8    .035       0
  5354.1     .07       0  5565.5      .1       0  5767.2    .035       0
#Block Obstruct= 2 , 0
         4149.35 1472.69
Bank Sta=4970.1,5030.4
XS Rating Curve= 0 ,0
Exp/Cntr=0.3,0.1