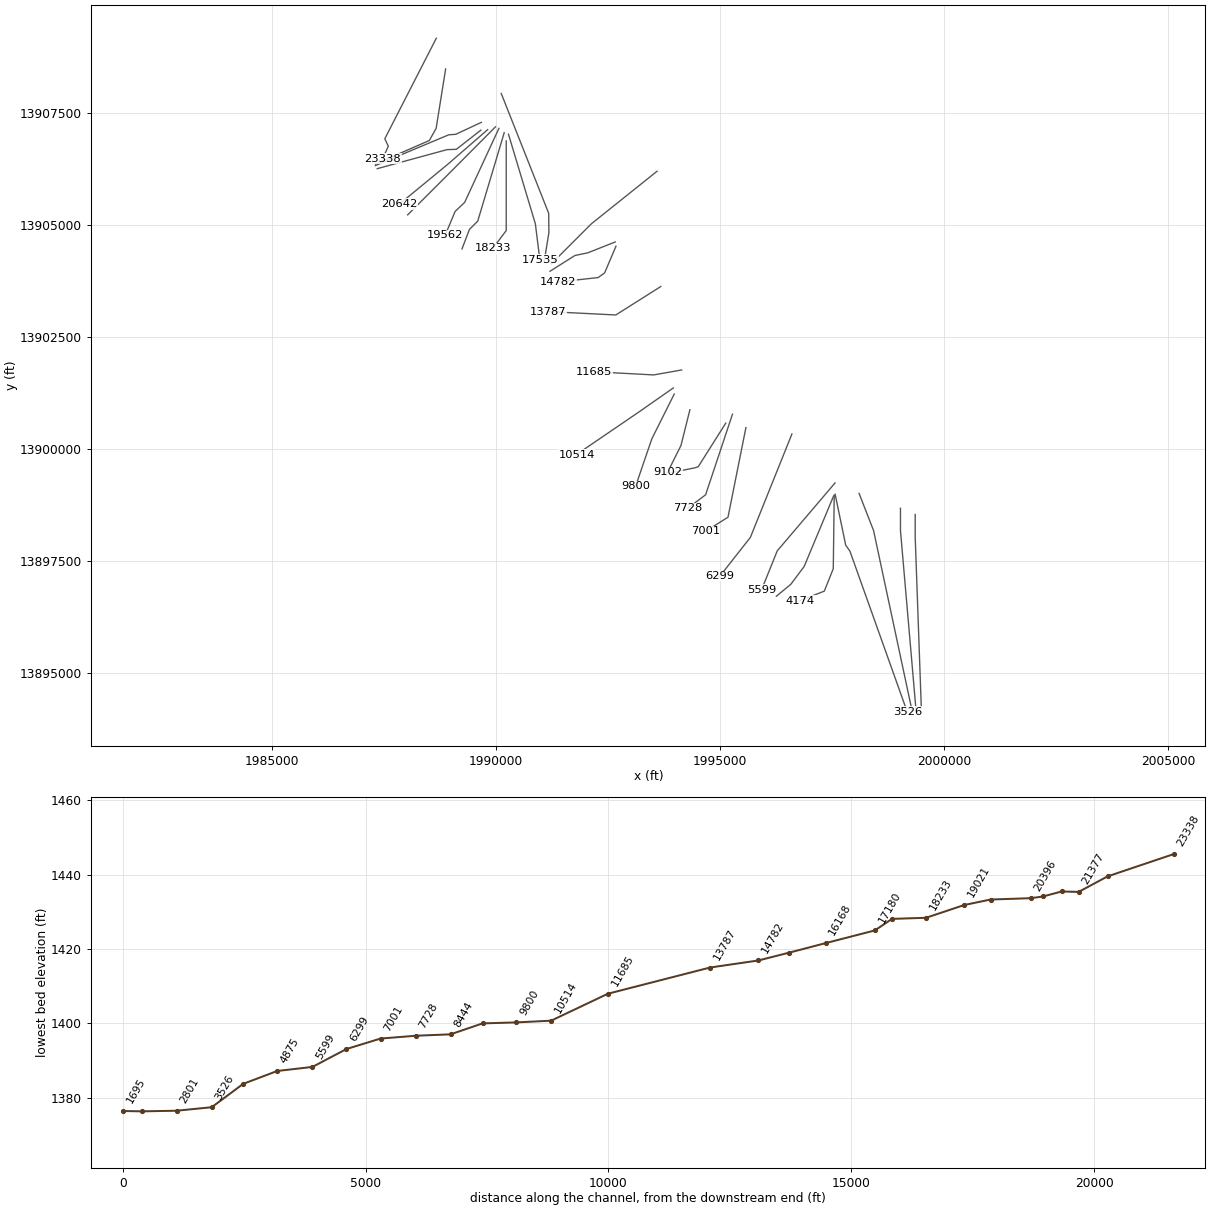
HEC-RAS study Cypress Creek.prj: Cypress Creek Base Level Engineering

--- Cypress Creek.g01 (geometry) --- (continued)

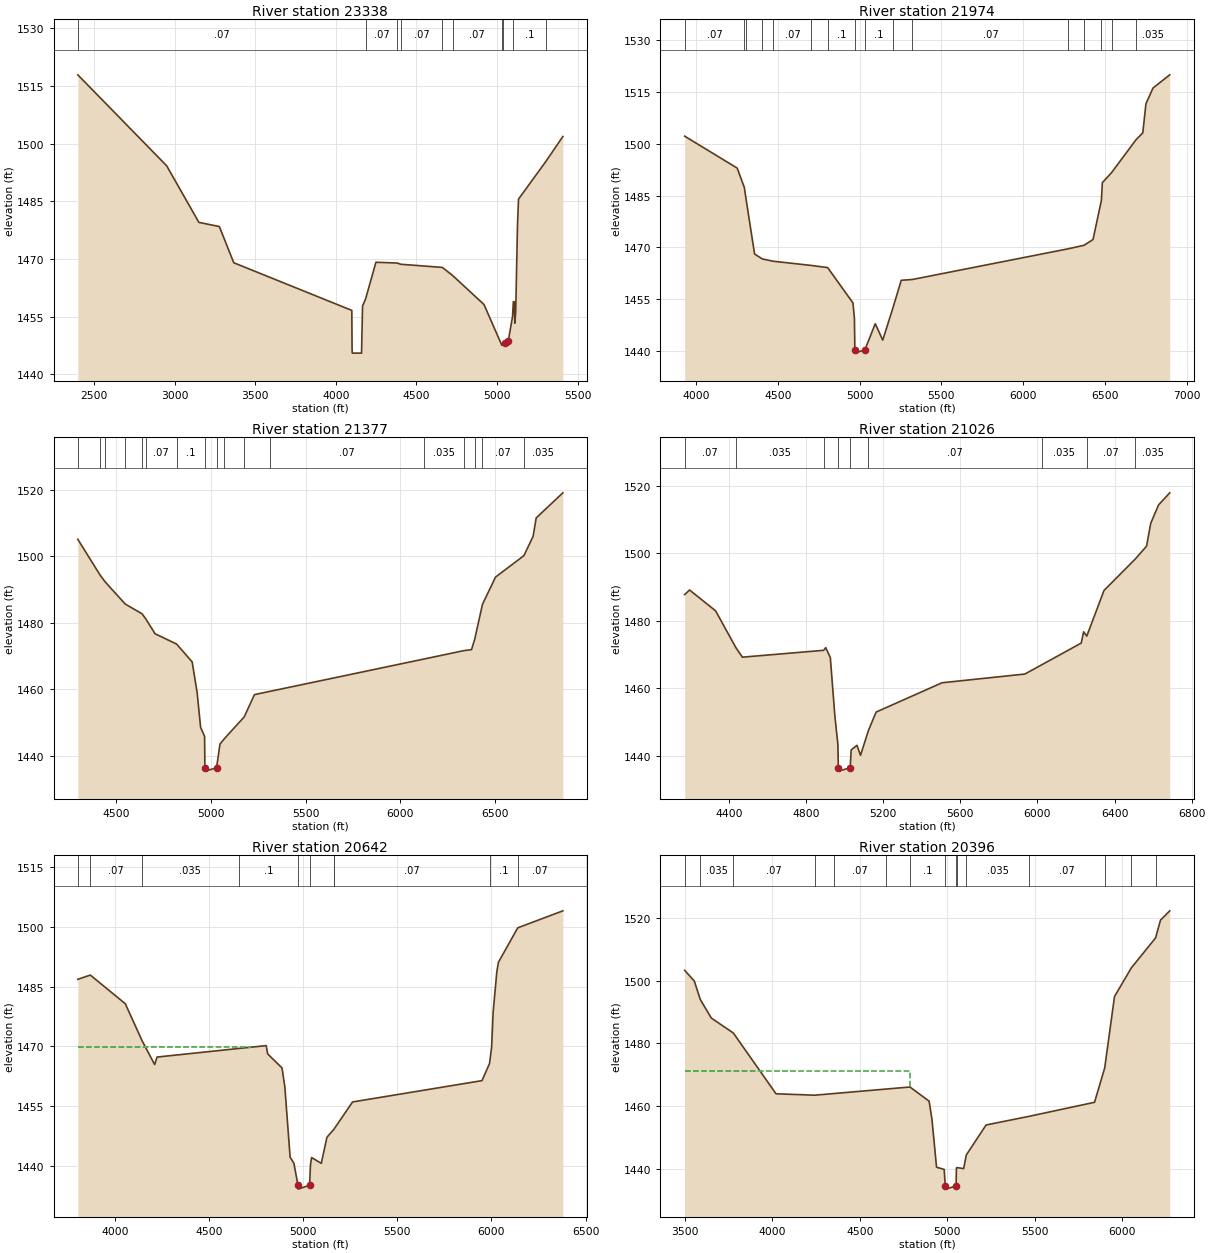
Type RM Length L Ch R = 1 ,23338   ,1364,1364,1364
BEGIN DESCRIPTION:
Cypress Creek 31.3
END DESCRIPTION:
XS GIS Cut Line= 4
      1988663.58     13909167.09      1987514.28     13906923.05
      1987592.97     13906756.93      1987466.82     13906478.53
#Sta/Elev= 30
  2397.8 1517.87  2949.6 1494.21  3149.4 1479.51  3276.5 1478.42  3365.8 1469.01
  4098.6 1456.62  4100.2 1446.51  4101.7 1445.51    4159 1445.51  4165.2 1457.72
  4184.61459.681  4248.4 1469.14    43801468.933  4402.41468.615  4660.21467.802
  4723.71465.721    4919 1458.15  5030.1 1447.53  5036.11447.747  5046.7 1448.13
  5069.4 1448.57  5096.41455.086  5101.2 1458.89  5106.4 1458.89  5110.2 1453.29
  5115.9 1456.24  5126.9  1478.7  5133.3 1485.55  5303.6 1495.38  5408.5 1501.83
#Mann= 10 ,-1 , 0
  2397.8     .07       0  4184.6     .07       0    4380    .035       0
  4402.4     .07       0  4660.2    .035       0  4723.7     .07       0
  5030.1      .1       0  5036.1     .05       0  5096.4      .1       0
  5303.6    .035       0
#Block Obstruct= 2 , 0
         4329.55 1468.49
Bank Sta=5046.7,5069.4
XS Rating Curve= 0 ,0
Exp/Cntr=0.3,0.1

Type RM Length L Ch R = 1 ,21974   ,597,597,597
BEGIN DESCRIPTION:
Cypress Creek 27.1
END DESCRIPTION:
XS GIS Cut Line= 4
      1988872.47     13908482.05      1988660.24     13907156.41
      1988508.94     13906885.23      1987304.68     13906359.43
#Sta/Elev= 30
  3929.9 1502.14  4251.3 1492.91  4295.1 1487.31    4304 1484.42  4357.6 1468.13
  4404.2 1466.71  4472.4 1466.03  4704.5 1464.82  4804.6  1464.2  4959.2 1454.01
  4968.3 1449.55  4970.9 1440.51  4972.4 1439.51  5032.6 1440.51  5095.9 1448.01
  5141.5 1443.27  5205.1 1452.76  5254.7 1460.53  5323.4 1460.77  6276.6 1469.63
  6372.9 1470.64  6427.8  1472.3    6479 1483.59  6484.9 1488.71  6541.5 1491.63
  6691.1 1501.12  6732.2 1503.07  6751.5 1511.49  6794.8 1516.03    6897 1519.84
#Mann= 16 ,-1 , 0
  3929.9     .07       0  4295.1      .1       0    4304     .07       0
  4404.2      .1       0  4472.4     .07       0  4704.5      .1       0
  4804.6      .1       0  4970.9     .05       0  5032.6      .1       0
  5205.1    .035       0  5323.4     .07       0  6276.6    .035       0
  6372.9     .07       0    6479    .035       0  6541.5     .07       0
  6691.1    .035       0
Bank Sta=4970.9,5032.6
XS Rating Curve= 0 ,0
Exp/Cntr=0.3,0.1

Type RM Length L Ch R = 1 ,21377   ,351,351,351
BEGIN DESCRIPTION:
Cypress Creek 28.0
END DESCRIPTION:
XS GIS Cut Line= 4
       1989668.7     13907289.46      1989097.78     13907023.23
      1988941.79      13907012.1      1987304.87     13906324.77
#Sta/Elev= 30
  4297.1 1505.09  4415.7 1494.25  4440.8 1492.32  4547.9 1485.59  4636.1 1482.68
  4655.1 1481.23  4705.1 1476.67    4819 1473.56  4901.2 1468.18  4927.6 1458.87
  4945.8 1448.47  4966.7  1445.8  4968.3 1436.33  4969.8 1435.33    5030 1436.33
  5047.9 1443.44  5071.3 1445.09    5176 1451.65  5230.1 1458.35  5311.9 1459.33
  6125.6 1469.06  6336.6 1471.59  6376.4 1471.87  6393.5 1475.06  6434.3 1485.52
  6503.3 1493.71  6653.1 1500.16  6701.7 1505.97    6718 1511.51  6858.8 1519.06
#Mann= 17 ,-1 , 0
  4297.1      .1       0  4415.7     .07       0  4440.8    .035       0
  4547.9     .07       0  4636.1    .035       0  4655.1     .07       0
    4819      .1       0  4968.3     .05       0    5030      .1       0
  5071.3     .07       0    5176    .035       0  5311.9     .07       0
  6125.6    .035       0  6336.6     .07       0  6393.5    .035       0
  6434.3     .07       0  6653.1    .035       0
Bank Sta=4968.3,5030
XS Rating Curve= 0 ,0
Exp/Cntr=0.3,0.1

Type RM Length L Ch R = 1 ,21026   ,384,384,384
BEGIN DESCRIPTION:
Cypress Creek 27.0
END DESCRIPTION:
XS GIS Cut Line= 4
      1989657.85     13907115.34      1989110.81      13906687.9
      1988904.84     13906681.25       1987345.7     13906256.03
#Sta/Elev= 30
  4169.8 1487.73  4195.2 1489.08  4330.3 1482.92    4435 1472.06  4469.2 1469.19
  4891.4 1471.22  4901.6 1472.02  4925.6 1469.02  4949.1 1451.72  4964.7 1443.39
  4966.8 1436.44  4968.3 1435.44  5028.5 1436.44  5033.7 1441.71  5063.7 1443.09
  5082.1 1440.12  5123.3  1447.5    5163 1452.93    5505 1461.61  5934.7 1464.19
    6022 1466.93    6227 1473.36  6239.5  1476.7    6256 1475.44  6345.2 1488.94
  6508.3 1498.31    6566 1502.06  6587.7 1508.84  6628.2 1514.27  6686.2 1517.86
#Mann= 9 ,-1 , 0
  4169.8     .07       0    4435    .035       0  4891.4      .1       0
  4966.8     .05       0  5028.5      .1       0  5123.3     .07       0
    6022    .035       0    6256     .07       0  6508.3    .035       0
Bank Sta=4966.8,5028.5
XS Rating Curve= 0 ,0
Exp/Cntr=0.3,0.1

Type RM Length L Ch R = 1 ,20642   ,246,246,246
BEGIN DESCRIPTION:
Cypress Creek 26.1
END DESCRIPTION:
XS GIS Cut Line= 3
      1989810.74      13907127.1      1988917.11     13906351.34
      1987841.96     13905466.37
#Sta/Elev= 30
  3803.3 1486.84  3869.7 1487.92  4055.6 1480.71  4144.4 1471.44  4211.5 1465.41
  4224.3  1467.3  4658.3 1469.46  4803.8 1470.18  4811.7 1468.09  4887.8 1464.56
  4902.7 1459.87  4930.9 1442.11  4950.8 1440.62  4972.6 1435.09  4974.1 1434.09
  5034.3 1435.09  5038.9 1440.19  5044.8 1442.03  5096.5 1440.58  5126.3 1447.13
  5162.8  1449.1  5262.4 1456.01  5949.8 1461.37  5989.7 1465.64    6001 1469.84
  6009.1 1478.65  6028.7 1488.81  6037.2 1491.14  6139.6 1499.79  6379.2 1504.07
#Mann= 10 ,-1 , 0
  3803.3    .035       0  3869.7     .07       0  4144.4    .035       0
  4658.3      .1       0  4972.6     .05       0  5034.3      .1       0
  5162.8    .035       0  5162.8     .07       0  5989.7      .1       0
  6139.6     .07       0
#XS Ineff= 2 , 0
         4722.78 1469.92
Permanent Ineff=
       F       F
Bank Sta=4972.6,5034.3
XS Rating Curve= 0 ,0
Exp/Cntr=0.3,0.1

Type RM Length L Ch R = 1 ,20396   ,834,834,834
BEGIN DESCRIPTION:
Cypress Creek 26.0
END DESCRIPTION:
XS GIS Cut Line= 3
      1989984.98     13907189.76        1988925.       13906125.
      1988025.01     13905225.01
#Sta/Elev= 30
  3497.7 1503.26  3552.7 1499.88  3587.2 1493.97  3650.2 1488.08  3776.2 1483.32
  4020.4 1463.98    4241 1463.53  4352.4 1464.06  4651.1 1465.49  4786.6 1466.14
  4896.3 1461.64  4912.5  1455.9  4938.8 1440.61  4982.5 1439.92  4988.7 1434.64
  4990.2 1433.64  5050.5 1434.64  5052.5 1440.39  5057.3  1440.5  5093.9 1440.16
  5108.9 1444.49  5222.2 1454.05  5470.5 1456.83  5842.7 1461.27  5900.9 1472.21
    5957 1494.93  6052.8 1504.01  6191.9 1513.58  6220.1 1519.23  6272.9  1522.2
#Mann= 15 ,-1 , 0
  3497.7     .07       0  3587.2    .035       0  3776.2     .07       0
    4241    .035       0  4352.4     .07       0  4651.1    .035       0
  4786.6      .1       0  4988.7     .05       0  5050.5      .1       0
  5057.3     .07       0  5108.9    .035       0  5470.5     .07       0
  5900.9      .1       0  6052.8     .07       0  6191.9      .1       0
#XS Ineff= 2 , 0
         4784.09 1471.14
Permanent Ineff=
       F       F
Bank Sta=4988.7,5050.5
XS Rating Curve= 0 ,0
Exp/Cntr=0.3,0.1

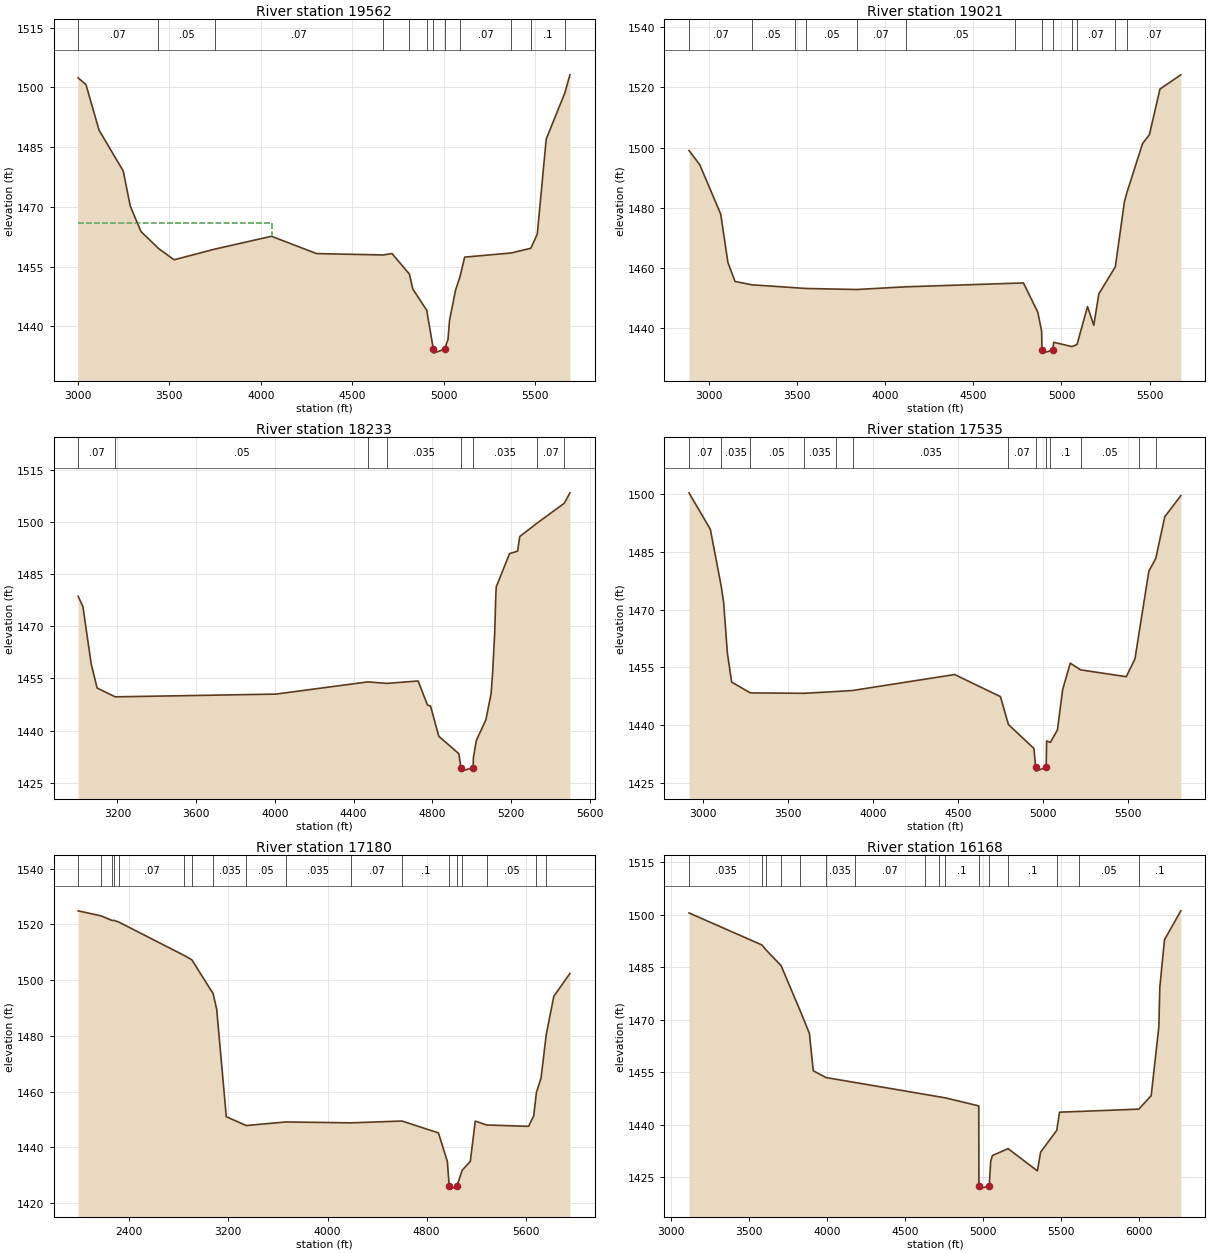
Type RM Length L Ch R = 1 ,19562   ,541,541,541
BEGIN DESCRIPTION:
Cypress Creek 25.0
END DESCRIPTION:
XS GIS Cut Line= 4
      1990061.41     13907155.44      1989296.85       13905503.
      1989084.24     13905301.45      1988862.76     13904772.13
#Sta/Elev= 30
  3002.2 1502.39  3045.1 1500.71  3116.5 1489.27  3248.7 1479.01  3286.9 1470.24
  3345.6 1463.81  3441.1 1459.57  3526.5 1456.71    3749 1459.39  4058.6 1462.61
  4305.2 1458.27  4668.9 1457.92  4717.4 1458.28  4812.6 1453.12  4830.7 1449.41
  4907.1 1444.05  4943.4 1434.27  4944.9 1433.27  5005.2 1434.27  5023.6 1436.76
  5031.6 1441.44  5064.9 1449.13  5088.7 1452.41  5114.5 1457.38  5368.1 1458.42
  5476.2 1459.61  5511.3 1463.15  5560.1 1487.02  5661.2 1498.54  5689.7 1503.16
#Mann= 12 ,-1 , 0
  3002.2     .07       0  3441.1     .05       0    3749     .07       0
  4668.9    .035       0  4812.6     .07       0  4907.1      .1       0
  4943.4     .05       0  5005.2      .1       0  5088.7     .07       0
  5368.1    .035       0  5476.2      .1       0  5661.2     .07       0
#XS Ineff= 2 , 0
         4061.69 1465.92
Permanent Ineff=
       F       F
Bank Sta=4943.4,5005.2
XS Rating Curve= 0 ,0
Exp/Cntr=0.3,0.1

Type RM Length L Ch R = 1 ,19021   ,788,788,788
BEGIN DESCRIPTION:
Cypress Creek 24.0
END DESCRIPTION:
XS GIS Cut Line= 4
      1990179.75      13907058.9       1989589.2     13905086.62
      1989403.16     13904898.37      1989237.04     13904464.23
#Sta/Elev= 30
  2888.4 1499.06  2949.2 1494.36  3068.2 1477.92  3108.9 1461.89  3149.3  1455.6
  3244.5 1454.48  3487.9 1453.51  3551.3 1453.26    3839 1452.92  4116.9 1453.81
  4738.8 1455.01  4784.3  1455.1  4865.7 1445.42  4887.6 1439.07  4889.7  1432.8
  4891.2  1431.8  4951.5  1432.8  4955.7  1435.4  5059.9 1433.97  5088.3 1434.68
  5147.7 1447.27  5183.3 1441.05  5211.9 1451.47  5305.6 1460.48  5357.1 1482.15
    5372 1485.26  5459.9 1501.39  5498.5  1504.3  5558.5 1519.47  5676.7 1524.18
#Mann= 13 ,-1 , 0
  2888.4     .07       0  3244.5     .05       0  3487.9     .07       0
  3551.3     .05       0    3839     .07       0  4116.9     .05       0
  4738.8    .035       0  4889.7     .05       0  4951.5    .035       0
  5059.9      .1       0  5088.3     .07       0  5305.6      .1       0
    5372     .07       0
Bank Sta=4889.7,4951.5
XS Rating Curve= 0 ,0
Exp/Cntr=0.3,0.1

Type RM Length L Ch R = 1 ,18233   ,698,698,698
BEGIN DESCRIPTION:
Cypress Creek 23.0
END DESCRIPTION:
XS GIS Cut Line= 3
        1990225.     13906874.99        1990225.       13904875.
      1989924.99     13904474.99
#Sta/Elev= 30
  2999.9 1478.65  3024.2 1475.72  3066.2 1459.23  3096.2 1452.27  3188.4 1449.72
  4005.2 1450.51  4472.1 1454.02  4570.5 1453.59  4728.2 1454.29    4776 1447.35
  4791.2 1447.11  4833.2  1438.4  4935.2 1433.36    4946 1429.36  4947.5 1428.36
  5007.9 1429.36    5009 1432.16  5024.2 1437.18  5072.8 1443.15    5099 1450.59
  5106.5 1456.31  5117.8 1468.44  5122.8 1478.61  5125.3 1481.34  5192.8 1490.91
    5234 1491.62  5244.9 1495.82  5331.7 1499.62  5471.1 1505.39  5499.9 1508.39
#Mann= 8 ,-1 , 0
  2999.9     .07       0  3188.4     .05       0  4472.1     .07       0
  4570.5    .035       0    4946     .05       0  5007.9    .035       0
  5331.7     .07       0  5471.1      .1       0
Bank Sta=4946,5007.9
XS Rating Curve= 0 ,0
Exp/Cntr=0.3,0.1

Type RM Length L Ch R = 1 ,17535   ,355,355,355
BEGIN DESCRIPTION:
Cypress Creek 22.0
END DESCRIPTION:
XS GIS Cut Line= 3
      1990275.01     13907024.96        1990875.       13905025.
      1990974.99     13904225.04
#Sta/Elev= 30
  2916.1 1500.38  3041.7 1490.88  3105.9 1476.04    3120 1471.79  3141.9 1458.74
  3166.9  1451.2  3277.1  1448.4  3591.9 1448.29  3778.4 1448.75  3880.2 1449.03
  4479.3 1453.17  4748.7 1447.43  4795.8 1440.17  4945.9 1433.96  4955.9 1429.07
  4957.4 1428.07  5017.8 1429.07  5020.6  1435.9  5042.8 1435.55    5084 1438.76
  5114.8 1449.26  5159.6 1456.12  5220.8 1454.38  5489.2 1452.61  5540.6 1457.25
  5566.7 1464.61  5622.2 1480.02  5662.8 1483.34  5715.9 1494.17  5810.3 1499.64
#Mann= 13 ,-1 , 0
  2916.1     .07       0  3105.9    .035       0  3277.1     .05       0
  3591.9    .035       0  3778.4     .05       0  3880.2    .035       0
  4795.8     .07       0  4955.9     .05       0  5017.8     .07       0
  5042.8      .1       0  5220.8     .05       0  5566.7     .07       0
  5662.8      .1       0
Bank Sta=4955.9,5017.8
XS Rating Curve= 0 ,0
Exp/Cntr=0.3,0.1

Type RM Length L Ch R = 1 ,17180   ,1012,1012,1012
BEGIN DESCRIPTION:
Cypress Creek 21.0
END DESCRIPTION:
XS GIS Cut Line= 5
      1990113.27     13907934.91      1990472.89     13907026.76
      1991172.76     13905259.37      1991177.19     13904825.28
      1991070.88     13904178.55
#Sta/Elev= 30
  1988.4  1524.9  2174.3 1523.08  2262.7 1521.43  2278.8 1521.48  2319.2  1520.8
  2844.5 1508.87  2905.7 1507.31  3076.9  1495.2  3106.1 1489.58  3183.6 1450.96
  3344.5  1447.8    3664 1449.08  4189.7 1448.76  4600.8 1449.42  4894.8 1445.15
  4966.8 1434.91  4981.8 1425.96  4983.3 1424.96  5043.7 1425.96  5086.4 1431.72
  5152.2 1434.94  5191.9 1449.39    5283    1448    5622 1447.51  5663.6 1451.27
  5685.1 1459.67  5722.4 1464.78  5764.6 1480.51  5825.7  1494.2  5955.6 1502.42
#Mann= 18 ,-1 , 0
  1988.4     .07       0  2174.3    .035       0  2262.7     .07       0
  2278.8    .035       0  2319.2     .07       0  2844.5    .035       0
  2905.7     .07       0  3076.9    .035       0  3344.5     .05       0
    3664    .035       0  4189.7     .07       0  4600.8      .1       0
  4981.8     .05       0  5043.7      .1       0  5086.4      .1       0
    5283     .05       0  5685.1     .07       0  5764.6      .1       0
Bank Sta=4981.8,5043.7
XS Rating Curve= 0 ,0
Exp/Cntr=0.3,0.1

Type RM Length L Ch R = 1 ,16168   ,756,756,756
BEGIN DESCRIPTION:
Cypress Creek 20.0
END DESCRIPTION:
XS GIS Cut Line= 4
      1993591.85     13906198.48        1993125.       13905825.
        1992125.       13905025.      1991224.99     13904124.99
#Sta/Elev= 30
  3116.9 1500.47  3583.9 1491.32  3611.2 1489.86    3707  1485.4  3830.1 1472.41
  3888.1 1466.08    3913 1455.37  3994.4 1453.43  4179.5 1452.03  4631.7  1448.6
  4718.1 1447.94    4760 1447.62  4973.5 1445.33  4974.2 1422.55  4975.7 1421.55
  5040.8 1422.55  5049.9 1429.45  5060.9 1431.15  5161.6 1433.12    5349 1426.76
  5369.8 1432.12  5473.3 1438.35  5491.1 1443.54  5618.6 1443.75  5999.2 1444.41
  6078.3 1448.26  6127.5    1468  6133.5 1479.18  6163.6 1492.81  6268.2 1501.07
#Mann= 16 ,-1 , 0
  3116.9    .035       0  3583.9      .1       0  3611.2    .035       0
    3707      .1       0  3830.1     .07       0  3994.4    .035       0
  4179.5     .07       0  4631.7    .035       0  4718.1     .07       0
    4760      .1       0  4974.2     .05       0  5040.8      .1       0
  5161.6      .1       0  5473.3    .035       0  5618.6     .05       0
  5999.2      .1       0
Bank Sta=4974.2,5040.8
XS Rating Curve= 0 ,0
Exp/Cntr=0.3,0.1

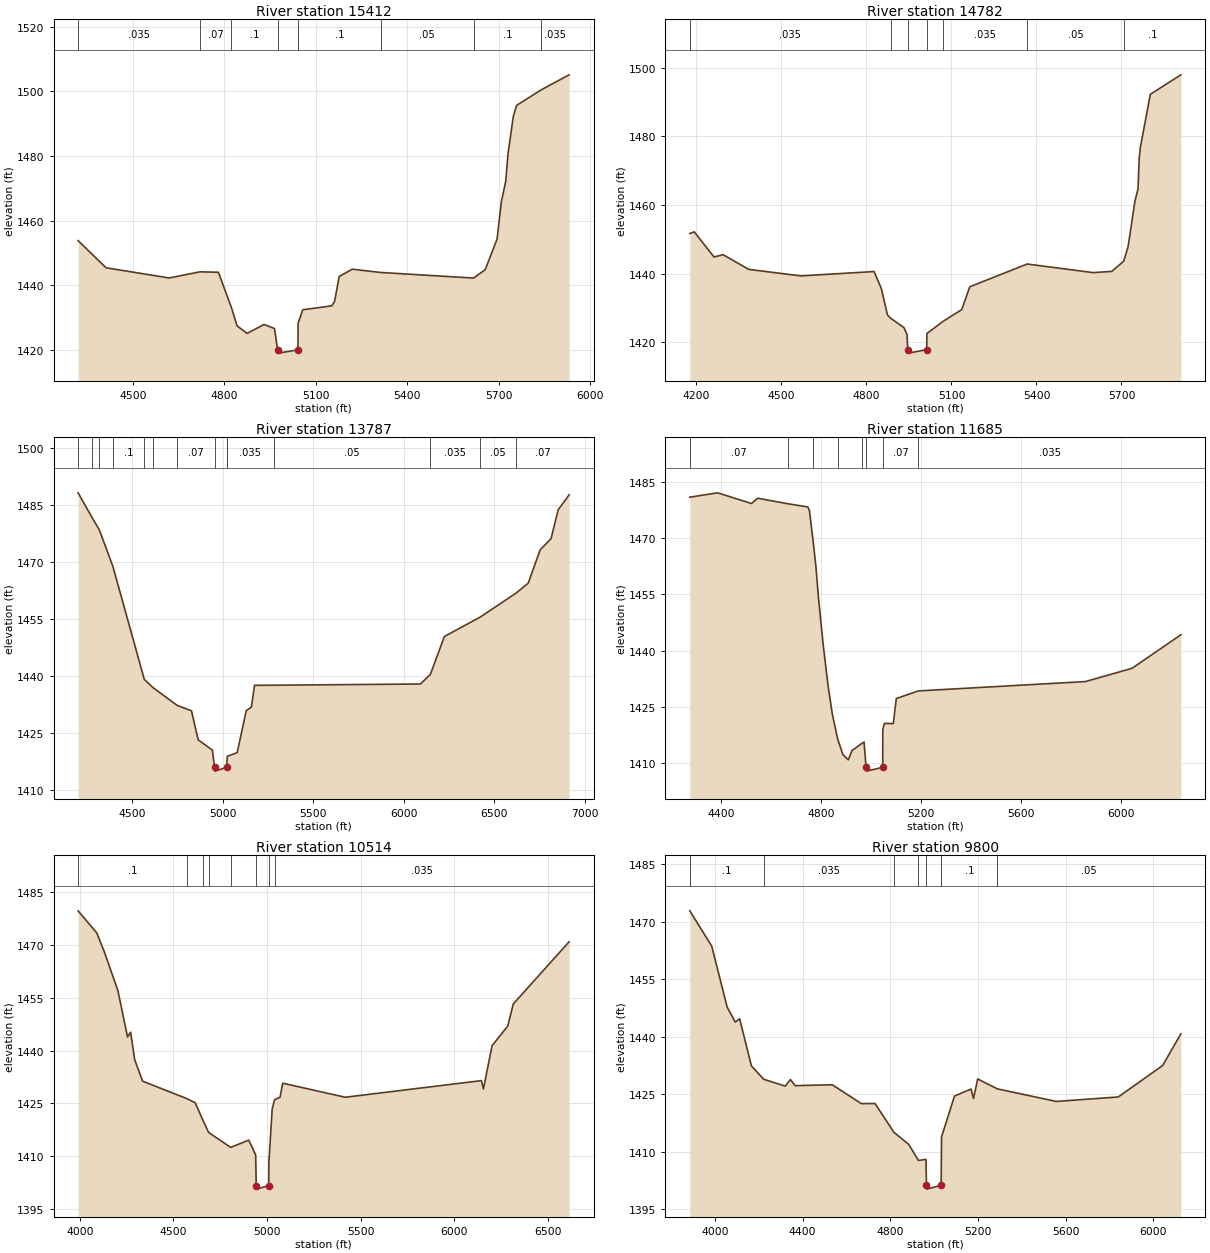
Type RM Length L Ch R = 1 ,15412   ,630,630,630
BEGIN DESCRIPTION:
Cypress Creek 19.0
END DESCRIPTION:
XS GIS Cut Line= 4
      1992656.69     13904619.32      1992047.59      13904377.9
      1991759.67      13904318.1      1991201.55     13903965.95
#Sta/Elev= 30
  4320.9  1453.8  4412.8 1445.39  4619.4 1442.24  4720.5 1444.14  4780.7 1444.01
  4823.6 1433.02    4842 1427.41  4874.8 1425.07  4930.3 1427.84  4964.6 1426.59
  4974.8 1419.97  4976.3 1418.97  5041.4 1419.97  5041.8 1428.19  5057.1 1432.39
  5152.1 1433.61  5161.3 1434.95  5176.6 1442.71  5219.5 1444.96  5312.1 1443.95
  5616.7 1442.21    5655 1444.81    5694 1454.29  5707.9 1465.78  5722.4 1472.24
  5729.5 1480.42  5747.1 1492.25  5757.8 1495.67    5838 1500.46  5930.1 1505.14
#Mann= 8 ,-1 , 0
  4320.9    .035       0  4720.5     .07       0  4823.6      .1       0
  4974.8     .05       0  5041.4      .1       0  5312.1     .05       0
  5616.7      .1       0    5838    .035       0
Bank Sta=4974.8,5041.4
XS Rating Curve= 0 ,0
Exp/Cntr=0.3,0.1

Type RM Length L Ch R = 1 ,14782   ,995,995,995
BEGIN DESCRIPTION:
Cypress Creek 18.0
END DESCRIPTION:
XS GIS Cut Line= 4
        1992675.     13904525.01      1992420.69     13903928.19
        1992275.       13903825.      1991375.02       13903725.
#Sta/Elev= 30
  4176.8 1451.73  4192.4 1452.22  4262.2 1444.89  4294.2 1445.56  4384.8 1441.28
  4568.6 1439.38  4826.9 1440.65  4852.8 1435.67  4874.3 1427.99  4885.6 1427.04
  4932.4 1424.32  4943.2 1422.32    4946 1417.88  4947.5 1416.88  5012.6 1417.88
  5013.6 1422.61  5070.7 1426.14  5136.4 1429.57  5164.8 1436.21  5367.2 1442.84
  5599.5 1440.34  5665.9 1440.69  5707.7 1443.65  5723.2  1447.8  5747.4 1461.08
  5758.5  1464.8  5762.5 1473.56  5766.6 1476.82  5801.9 1492.29  5909.6 1497.96
#Mann= 7 ,-1 , 0
  4176.8    .035       0  4885.6      .1       0    4946     .05       0
  5012.6      .1       0  5070.7    .035       0  5367.2     .05       0
  5707.7      .1       0
Bank Sta=4946,5012.6
XS Rating Curve= 0 ,0
Exp/Cntr=0.3,0.1

Type RM Length L Ch R = 1 ,13787   ,2102,2102,2102
BEGIN DESCRIPTION:
Cypress Creek 17.0
END DESCRIPTION:
XS GIS Cut Line= 3
      1993675.04     13903625.03      1992670.94      13902989.9
      1991151.76       13903066.
#Sta/Elev= 30
  4202.6 1488.13  4280.2  1481.6  4319.8 1478.39  4394.1 1468.86  4567.8  1439.1
  4616.7  1436.9  4749.9 1432.24  4828.2 1430.84  4865.2  1423.2  4943.4 1420.52
  4955.8 1415.98  4957.3 1414.98  5022.5 1415.98  5022.9 1416.32  5025.9 1418.87
  5080.4 1419.85  5130.4 1430.87  5158.7 1431.82  5176.1 1437.54  5282.7 1437.56
  6091.3 1437.88  6146.1  1440.4  6223.5 1450.36  6421.1 1455.47  6618.8 1461.76
    6686 1464.39  6752.1 1473.16  6812.2  1476.1  6851.2 1483.66  6911.8  1487.6
#Mann= 14 ,-1 , 0
  4202.6     .07       0  4280.2      .1       0  4319.8     .07       0
  4394.1      .1       0  4567.8     .07       0  4616.7      .1       0
  4749.9     .07       0  4955.8     .05       0  5022.5     .07       0
  5022.9    .035       0  5282.7     .05       0  6146.1    .035       0
  6421.1     .05       0  6618.8     .07       0
Bank Sta=4955.8,5022.5
XS Rating Curve= 0 ,0
Exp/Cntr=0.3,0.1

Type RM Length L Ch R = 1 ,11685   ,1171,1171,1171
BEGIN DESCRIPTION:
Cypress Creek 16.0
END DESCRIPTION:
XS GIS Cut Line= 3
      1994140.57     13901762.27      1993515.98     13901651.52
      1992187.11      13901722.4
#Sta/Elev= 30
  4274.4 1480.86  4385.6 1482.02  4521.5 1479.18  4545.9 1480.58  4666.9 1479.11
    4747 1478.26  4753.1 1477.26  4766.4 1469.96    4779 1462.44  4789.6 1453.85
  4807.9 1441.69  4828.1 1430.43  4844.5 1423.19    4866 1416.52  4887.1 1412.33
  4908.5 1410.95  4923.5 1413.41  4965.1 1415.42  4971.8 1415.68  4979.7 1408.94
  4981.2 1407.94  5046.4 1408.94  5046.7  1418.9  5052.7 1420.63  5088.7  1420.6
  5100.7 1427.26  5188.9 1429.29  5857.8 1431.78  6044.1 1435.31  6239.5 1444.24
#Mann= 8 ,-1 , 0
  4274.4     .07       0  4666.9      .1       0  4766.4      .1       0
    4866      .1       0  4965.1     .07       0  4979.7     .05       0
  5046.4     .07       0  5188.9    .035       0
Bank Sta=4979.7,5046.4
XS Rating Curve= 0 ,0
Exp/Cntr=0.3,0.1

Type RM Length L Ch R = 1 ,10514   ,714,714,714
BEGIN DESCRIPTION:
Mapping XS 2c7ec6cd
END DESCRIPTION:
XS GIS Cut Line= 3
      1993954.92     13901360.96      1993182.43      13900821.6
      1991792.93     13899873.66
#Sta/Elev= 30
  3990.5  1479.7  4090.1 1473.46  4131.2    1468  4203.5 1456.99  4254.8 1443.89
  4271.3 1445.24  4292.8 1437.44  4335.3 1431.34  4570.5  1426.4    4616 1425.23
  4659.9 1419.98  4688.1 1416.77  4805.7 1412.54  4902.8 1414.59  4939.6 1410.36
  4942.4 1401.68  4943.9 1400.68  5009.3 1401.68  5010.4 1408.34  5027.7 1423.39
  5040.2 1426.09  5069.7 1426.75  5084.2 1430.76  5418.3 1426.77    6146 1431.49
  6156.8 1429.11  6202.7  1441.4  6286.4 1446.97  6316.5 1453.27  6614.7 1470.92
#Mann= 8 ,-1 , 0
  3990.5      .1       0  4570.5     .07       0  4659.9      .1       0
  4688.1     .07       0  4805.7      .1       0  4942.4     .05       0
  5009.3      .1       0  5040.2    .035       0
Bank Sta=4942.4,5009.3
XS Rating Curve= 0 ,0
Exp/Cntr=0.3,0.1

Type RM Length L Ch R = 1 ,9800    ,698,698,698
BEGIN DESCRIPTION:
Cypress Creek 14.0
END DESCRIPTION:
XS GIS Cut Line= 3
      1993975.01     13901225.02        1993475.       13900225.
      1993111.91     13899163.86
#Sta/Elev= 30
  3885.8 1472.87  3985.7 1463.66  4056.1 1447.74  4093.2 1443.81  4113.1 1444.69
  4166.8 1432.38  4223.5 1428.88  4321.3 1427.11  4344.6 1428.83  4365.9 1427.23
  4535.7 1427.46  4667.8 1422.55  4730.5 1422.57  4816.8 1415.05  4884.6 1411.88
  4928.5 1407.71  4962.9 1407.99  4965.2 1401.22  4966.7 1400.22  5032.1 1401.22
  5033.8 1413.83  5092.9 1424.51  5168.5 1426.35  5179.6 1423.88  5198.7 1428.98
  5288.5 1426.39  5557.3 1423.11  5839.9 1424.28  6042.5  1432.5  6125.4 1440.77
#Mann= 7 ,-1 , 0
  3885.8      .1       0  4223.5    .035       0  4816.8     .07       0
  4928.5      .1       0  4965.2     .05       0  5032.1      .1       0
  5288.5     .05       0
Bank Sta=4965.2,5032.1
XS Rating Curve= 0 ,0
Exp/Cntr=0.3,0.1

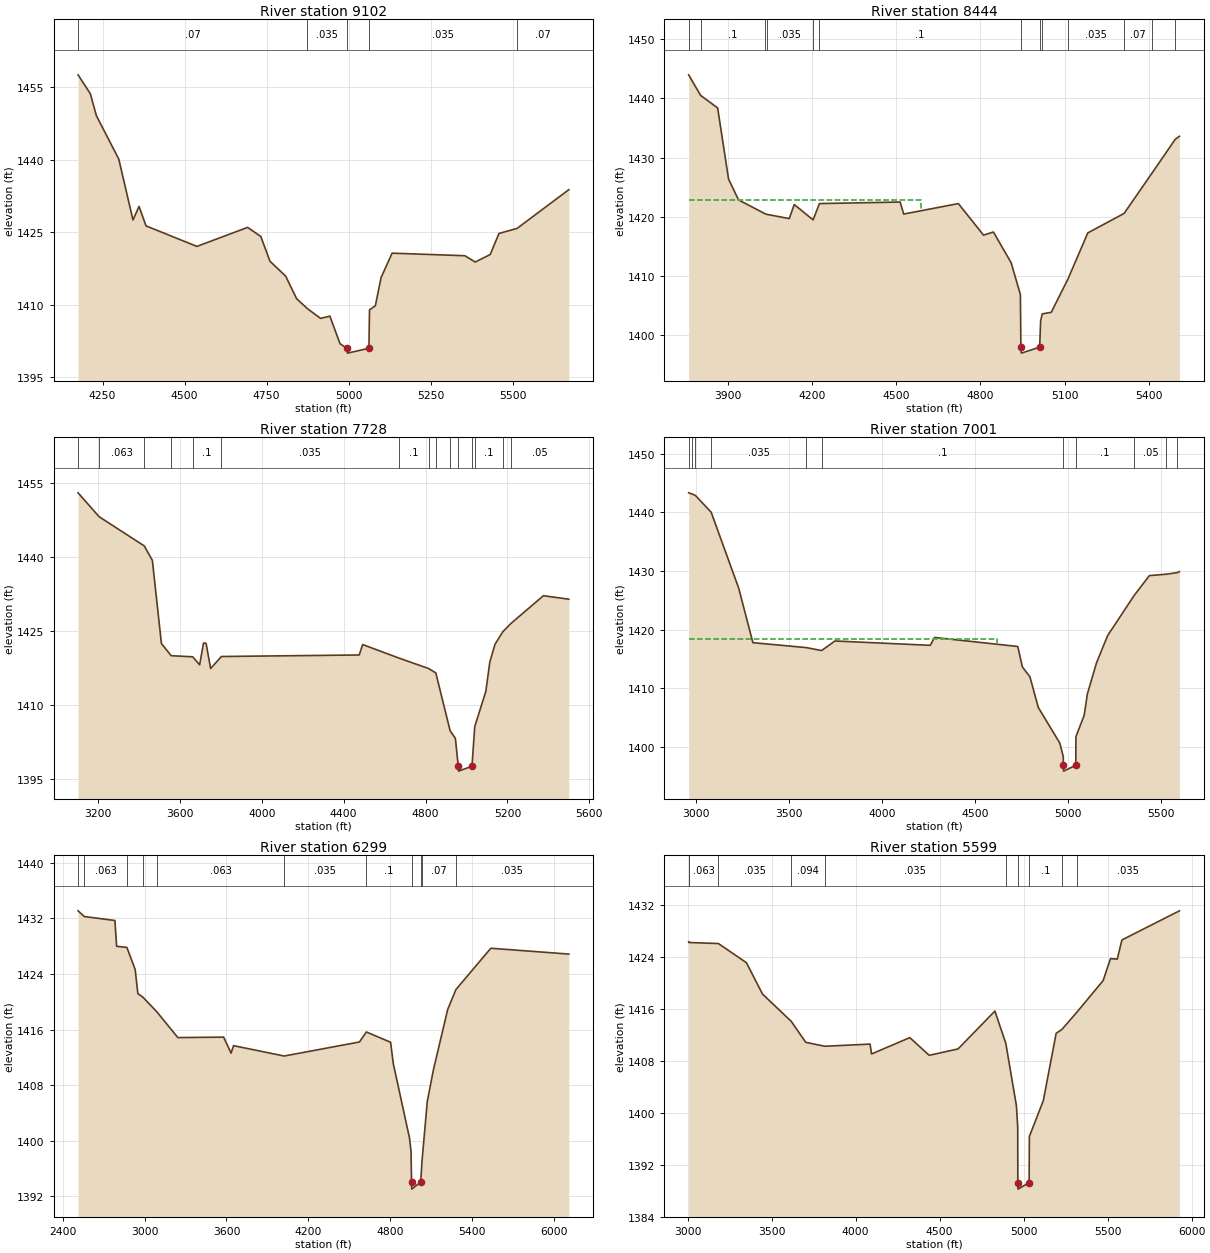
Type RM Length L Ch R = 1 ,9102    ,658,658,658
BEGIN DESCRIPTION:
Cypress Creek 13.0
END DESCRIPTION:
XS GIS Cut Line= 3
      1994324.99     13900874.96        1994125.       13900075.
        1993825.       13899475.
#Sta/Elev= 30
  4175.4 1457.58  4212.8 1453.66  4231.3  1449.1  4299.4 1440.14  4342.7 1427.53
  4361.2 1430.33  4382.4  1426.3  4537.5 1422.05  4692.1 1425.99  4732.3  1424.1
  4760.1 1418.98  4807.9  1415.9  4841.3 1411.23  4874.3 1409.16  4914.3 1407.14
  4942.6 1407.62  4973.7 1401.89  4994.8 1400.95  4996.3 1399.95  5061.7 1400.95
  5063.4 1408.91  5081.3 1409.76  5098.7 1415.59  5132.3 1420.65    5354 1420.12
  5385.6 1418.81  5431.2 1420.37    5458 1424.73  5513.2 1425.78  5670.8  1433.8
#Mann= 5 ,-1 , 0
  4175.4     .07       0  4874.3    .035       0  4994.8    .035       0
  5061.7    .035       0  5513.2     .07       0
Bank Sta=4994.8,5061.7
XS Rating Curve= 0 ,0
Exp/Cntr=0.3,0.1

Type RM Length L Ch R = 1 ,8444    ,716,716,716
BEGIN DESCRIPTION:
Cypress Creek 12.0
END DESCRIPTION:
XS GIS Cut Line= 4
      1995125.01     13900575.02      1994510.76      13899602.8
        1994425.       13899575.      1993924.96     13899474.99
#Sta/Elev= 30
  3759.5 1443.98    3802 1440.51  3862.8 1438.39  3901.7 1426.39  3937.3 1422.87
  4032.1 1420.53  4039.4 1420.42  4118.3 1419.72    4136 1422.09  4203.2  1419.5
  4225.8 1422.25  4513.6 1422.51  4526.4 1420.48  4721.2 1422.25  4810.9 1416.93
  4846.2 1417.45  4909.5 1412.27  4942.5 1406.88  4944.2 1398.01  4945.7 1397.01
  5011.2 1398.01  5014.6 1402.43  5020.2 1403.63  5052.6  1403.9  5112.5 1409.56
  5182.9  1417.3  5312.3 1420.59  5412.1 1427.41  5494.5 1433.09  5509.6 1433.61
#Mann= 13 ,-1 , 0
  3759.5    .035       0    3802      .1       0  4032.1     .07       0
  4039.4    .035       0  4203.2     .07       0  4225.8      .1       0
  4944.2     .05       0  5011.2      .1       0  5020.2      .1       0
  5112.5    .035       0  5312.3     .07       0  5412.1     .05       0
  5494.5     .07       0
#XS Ineff= 2 , 0
         4588.91 1422.93
Permanent Ineff=
       F       F
Bank Sta=4944.2,5011.2
XS Rating Curve= 0 ,0
Exp/Cntr=0.3,0.1

Type RM Length L Ch R = 1 ,7728    ,727,727,727
BEGIN DESCRIPTION:
Cypress Creek 11.0
END DESCRIPTION:
XS GIS Cut Line= 3
        1995275.     13900775.01        1994675.       13898975.
      1994275.06     13898675.05
#Sta/Elev= 30
  3102.6 1453.08  3205.3 1448.24  3426.2  1442.3  3465.5 1439.37  3509.8 1422.51
  3557.7 1420.04  3662.5 1419.82  3696.4 1418.19  3715.4 1422.62    3728 1422.54
  3750.1 1417.44  3802.6 1419.88  4476.1 1420.19  4492.7 1422.31    4668 1419.59
  4815.1 1417.44  4850.2 1416.55  4919.9 1404.84  4945.7 1403.28  4959.8 1397.63
  4961.3 1396.63  5026.8 1397.63  5040.3 1405.65  5094.6 1412.83  5113.8 1418.74
  5139.4 1422.37  5177.4  1424.9  5216.5 1426.56  5375.8 1432.21  5499.9  1431.5
#Mann= 15 ,-1 , 0
  3102.6    .035       0  3205.3    .063       0  3426.2      .1       0
  3557.7     .07       0  3662.5      .1       0  3802.6    .035       0
    4668      .1       0  4815.1     .07       0  4850.2      .1       0
  4919.9      .1       0  4959.8     .05       0  5026.8      .1       0
  5040.3      .1       0  5177.4     .07       0  5216.5     .05       0
Bank Sta=4959.8,5026.8
XS Rating Curve= 0 ,0
Exp/Cntr=0.3,0.1

Type RM Length L Ch R = 1 ,7001    ,702,702,702
BEGIN DESCRIPTION:
Cypress Creek 10.0
END DESCRIPTION:
XS GIS Cut Line= 3
        1995575.     13900474.98        1995175.       13898475.
       1994669.2     13898158.02
#Sta/Elev= 30
  2960.4  1443.3  2980.3 1443.08  2996.9 1442.84  3081.3 1439.99  3228.9 1427.08
  3305.4 1417.76  3592.7 1416.92  3674.5 1416.42  3746.3 1418.05  4258.4 1417.31
  4281.3 1418.65  4728.4 1417.11    4753 1413.64  4793.8 1411.94  4838.5 1406.73
  4954.4 1400.64  4973.1  1398.3  4973.2 1396.87  4974.7 1395.87  5040.2 1396.87
  5040.8 1401.74  5085.1 1405.37  5102.3 1409.02  5151.8 1414.36  5211.4 1418.98
  5355.1 1425.87  5435.5 1429.19  5526.3 1429.43  5583.7 1429.69  5596.9 1429.87
#Mann= 11 ,-1 , 0
  2960.4    .094       0  2980.3    .035       0  2996.9    .063       0
  3081.3    .035       0  3592.7    .063       0  3674.5      .1       0
  4973.2     .05       0  5040.2      .1       0  5355.1     .05       0
  5526.3    .035       0  5583.7     .05       0
#XS Ineff= 2 , 0
         4615.38 1418.38
Permanent Ineff=
       F       F
Bank Sta=4973.2,5040.2
XS Rating Curve= 0 ,0
Exp/Cntr=0.3,0.1

Type RM Length L Ch R = 1 ,6299    ,700,700,700
BEGIN DESCRIPTION:
Cypress Creek 9.0
END DESCRIPTION:
XS GIS Cut Line= 3
      1996601.95      13900333.1        1995675.       13898025.
      1994988.86     13897152.82
#Sta/Elev= 30
  2512.7 1433.07  2558.6 1432.25  2782.5 1431.68  2795.5 1427.97  2870.3 1427.81
  2931.3 1424.63  2950.7 1421.17  2988.1 1420.65  3089.6 1418.56  3244.2 1414.84
  3579.6 1414.91    3634 1412.61  3652.6 1413.68  4023.5 1412.19  4575.1 1414.21
  4625.7 1415.65  4803.4 1414.17  4822.9 1411.12  4941.8 1400.41  4953.3 1398.44
  4956.8 1394.05  4958.3 1393.05  5023.8 1394.05  5033.2 1396.99  5072.2 1405.65
    5117 1410.19  5221.7 1418.88  5282.1 1421.75  5537.9 1427.69  6109.7 1426.85
#Mann= 11 ,-1 , 0
  2512.7    .035       0  2558.6    .063       0  2870.3    .035       0
  2988.1    .063       0  3089.6    .063       0  4023.5    .035       0
  4625.7      .1       0  4956.8     .05       0  5023.8      .1       0
  5033.2     .07       0  5282.1    .035       0
Bank Sta=4956.8,5023.8
XS Rating Curve= 0 ,0
Exp/Cntr=0.3,0.1

Type RM Length L Ch R = 1 ,5599    ,724,724,724
BEGIN DESCRIPTION:
Cypress Creek 8.0
END DESCRIPTION:
XS GIS Cut Line= 3
      1997564.08     13899240.11        1996275.       13897725.
      1995926.43     13896860.74
#Sta/Elev= 30
  3006.2 1426.35  3007.5 1426.23  3183.4 1426.07  3349.9 1423.12  3445.7 1418.29
  3616.5 1414.09  3703.2 1410.85  3816.8 1410.25    4086 1410.58  4094.8 1409.06
  4322.5 1411.58  4437.9 1408.85  4609.8 1409.84    4829 1415.67    4894 1410.69
    4957  1401.1  4964.9 1397.75  4965.5 1389.24    4967 1388.24  5032.8 1389.24
  5034.2 1396.36  5117.2 1401.87  5193.6 1412.24  5227.8 1412.84  5315.3 1415.44
  5473.2 1420.36    5517 1423.74  5557.4 1423.67    5585 1426.62  5927.4 1431.11
#Mann= 10 ,-1 , 0
  3006.2    .094       0  3007.5    .063       0  3183.4    .035       0
  3616.5    .094       0  3816.8    .035       0    4894      .1       0
  4965.5     .05       0  5032.8      .1       0  5227.8      .1       0
  5315.3    .035       0
Bank Sta=4965.5,5032.8
XS Rating Curve= 0 ,0
Exp/Cntr=0.3,0.1

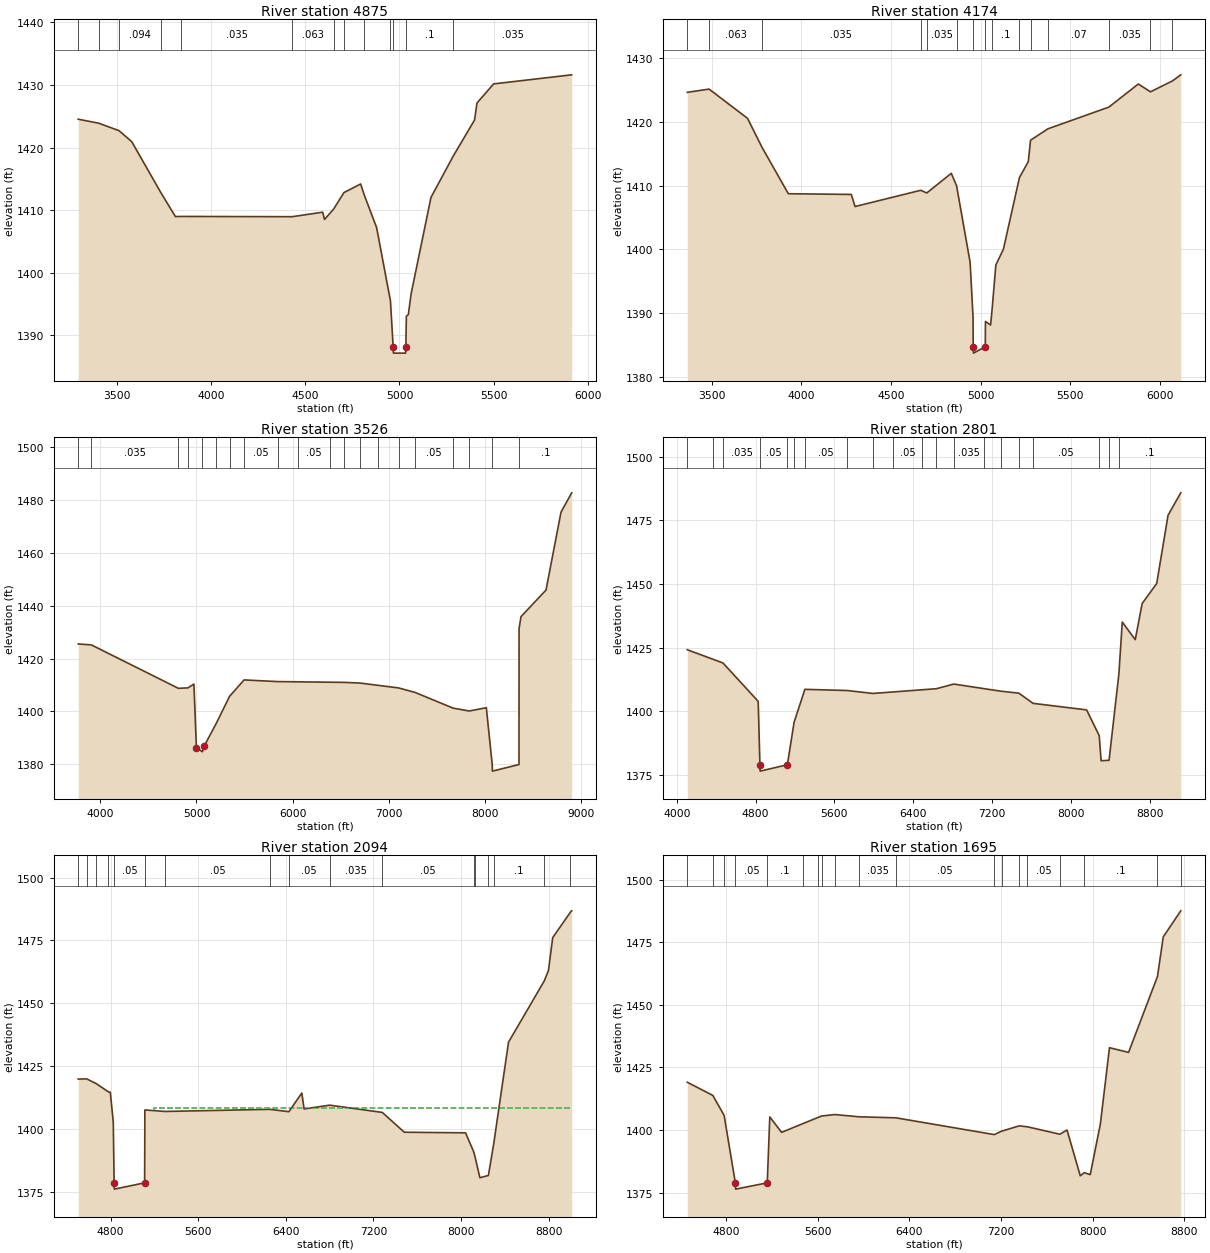
Type RM Length L Ch R = 1 ,4875    ,701,701,701
BEGIN DESCRIPTION:
Cypress Creek 7.0
END DESCRIPTION:
XS GIS Cut Line= 4
       1997532.5      13898949.4        1996875.       13897375.
        1996575.       13896975.      1996254.81     13896711.43
#Sta/Elev= 30
  3293.6 1424.53  3402.3 1423.89  3510.5  1422.7  3578.2 1420.93  3732.7 1412.79
  3809.8 1408.97  3840.7 1408.99    4430 1408.95    4592 1409.67  4601.7 1408.51
  4650.7 1410.19  4704.8  1412.8  4793.6 1414.18  4812.8 1412.42  4878.5 1407.21
  4948.4 1396.07  4951.9 1395.54  4966.3 1388.15  4967.8 1387.15  5032.2 1387.15
  5033.7 1388.15  5036.5 1393.05  5046.9  1393.3  5061.9 1396.65  5167.2 1412.03
  5285.5 1418.64  5398.6  1424.4  5411.5 1427.11  5499.8 1430.17  5914.5 1431.62
#Mann= 13 ,-1 , 0
  3293.6    .094       0  3402.3    .035       0  3510.5    .094       0
  3732.7    .063       0  3840.7    .035       0    4430    .063       0
  4650.7    .035       0  4704.8    .063       0  4812.8    .035       0
  4948.4      .1       0  4966.3     .05       0  5033.7      .1       0
  5285.5    .035       0
Bank Sta=4966.3,5033.7
XS Rating Curve= 0 ,0
Exp/Cntr=0.3,0.1

Type RM Length L Ch R = 1 ,4174    ,648,648,648
BEGIN DESCRIPTION:
Cypress Creek 6.0
END DESCRIPTION:
XS GIS Cut Line= 4
      1997546.28     13898966.76        1997525.       13897325.
        1997325.       13896825.      1996790.99      13896615.1
#Sta/Elev= 30
  3362.7 1424.66  3484.4 1425.17  3699.2 1420.57  3779.7 1416.03  3926.8 1408.73
  4278.2 1408.62  4299.2 1406.72  4665.4 1409.27  4699.6 1408.85  4836.3 1411.94
  4865.9 1409.97  4941.3 1397.96  4957.6 1389.38  4958.6 1384.69  4960.1 1383.69
    5026 1384.69  5026.9 1388.67  5055.6 1388.11    5064 1390.55    5085 1397.54
    5127    1400  5216.8 1411.28    5266 1413.76  5278.6 1417.14  5375.8 1418.93
  5715.9 1422.34  5880.1 1425.97    5948 1424.74  6070.5 1426.45  6116.9 1427.41
#Mann= 15 ,-1 , 0
  3362.7    .094       0  3484.4    .063       0  3779.7    .035       0
  4665.4      .1       0  4699.6    .035       0  4865.9      .1       0
  4958.6     .05       0    5026      .1       0    5064      .1       0
  5216.8     .07       0  5278.6    .035       0  5375.8     .07       0
  5715.9    .035       0    5948     .07       0  6070.5    .035       0
Bank Sta=4958.6,5026
XS Rating Curve= 0 ,0
Exp/Cntr=0.3,0.1

Type RM Length L Ch R = 1 ,3526    ,725,725,725
BEGIN DESCRIPTION:
Cypress Creek 5.0
END DESCRIPTION:
XS GIS Cut Line= 4
      1997566.99     13898987.68      1997802.61     13897850.79
       1997896.4     13897718.02      1999176.05     13894127.97
#Sta/Elev= 30
  3769.3 1425.53  3906.1 1425.18  4811.6 1408.74  4911.4 1408.91  4973.2 1410.35
  4999.2 1386.22  5061.3 1384.73  5077.8 1386.74  5206.7 1395.53  5343.9 1405.69
  5495.3 1411.92  5843.7 1411.29  6053.9  1411.2  6387.9 1411.05    6534 1410.99
  6699.9 1410.74  6887.5 1409.88  7103.3 1408.89  7273.4  1407.2  7669.9 1401.25
  7837.6 1400.16    8016  1401.4  8077.3  1379.9  8079.3  1377.4  8355.9  1379.9
  8356.8  1431.4    8377 1435.88  8637.1 1445.93  8793.1  1475.4  8904.2 1482.73
#Mann= 20 ,-1 , 0
  3769.3    .094       0  3906.1    .035       0  4811.6      .1       0
  4911.4    .035       0  5061.3      .1       0  5206.7      .1       0
  5343.9    .035       0  5495.3     .05       0  5843.7     .05       0
  6053.9     .05       0  6387.9    .035       0    6534     .05       0
  6699.9    .035       0  6887.5     .05       0  7103.3    .035       0
  7273.4     .05       0  7669.9    .035       0  7837.6     .05       0
  8077.3    .035       0  8355.9      .1       0
#Block Obstruct= 2 , 0
                         6610.78         1410.86
Bank Sta=4999.2,5077.8
XS Rating Curve= 0 ,0
Exp/Cntr=0.3,0.1

Type RM Length L Ch R = 1 ,2801    ,707,707,707
BEGIN DESCRIPTION:
Cypress Creek 4.0
END DESCRIPTION:
XS GIS Cut Line= 3
      1998100.91     13899007.47        1998425.       13898175.
      1999284.31     13894150.15
#Sta/Elev= 30
  4106.4 1424.16  4364.4 1420.46  4468.7 1418.96  4826.3 1403.87  4843.9 1378.96
  4845.9 1376.46  5122.5 1378.96  5190.4 1395.62  5300.1  1408.6  5730.6 1408.13
  5989.7 1406.98  6195.8 1407.57  6491.2 1408.43  6634.9 1408.84  6811.6 1410.67
  7121.5 1408.85  7287.5 1407.88  7471.6  1407.1  7616.8 1403.09  8159.8 1400.52
  8287.8 1390.41    8307 1380.54  8387.7 1380.71  8487.6  1414.7  8521.8 1435.03
  8653.7 1428.12  8723.7 1442.33  8871.5 1450.19  8986.4 1476.97  9115.3 1485.81
#Mann= 20 ,-1 , 0
  4106.4    .094       0  4364.4    .063       0  4468.7    .035       0
  4843.9     .05       0  5122.5      .1       0  5190.4     .07       0
  5300.1     .05       0  5730.6    .035       0  5989.7     .07       0
  6195.8     .05       0  6491.2    .035       0  6634.9     .05       0
  6811.6    .035       0  7121.5     .05       0  7287.5    .035       0
  7471.6    .035       0  7616.8     .05       0  8287.8      .1       0
  8387.7     .07       0  8487.6      .1       0
#Block Obstruct= 2 , 0
                         7077.84         1410.02
Bank Sta=4843.9,5122.5
XS Rating Curve= 0 ,0
Exp/Cntr=0.3,0.1

Type RM Length L Ch R = 1 ,2094    ,399,399,399
BEGIN DESCRIPTION:
Cypress Creek 3.0
END DESCRIPTION:
XS GIS Cut Line= 3
        1999025.     13898674.96        1999025.       13898175.
      1999370.85     13894183.01
#Sta/Elev= 30
  4504.4 1419.98  4581.7 1420.06  4668.4 1418.19  4779.8 1414.91  4797.7 1414.75
  4824.7 1402.78  4832.4 1378.79  4834.4 1376.29    5111 1378.79  5113.2 1407.72
  5297.9 1407.12  6254.1 1407.97  6428.6 1407.03  6546.5 1414.44  6567.6 1408.12
  6801.4 1409.62  7281.5 1406.74    7483 1398.88  8041.9 1398.64    8115 1391.28
  8127.5 1389.33  8173.1 1380.82  8250.6 1381.71  8299.2 1394.25  8434.5 1434.63
  8760.8 1458.93  8798.9 1463.03  8838.1 1476.13  8999.7 1486.23  9011.3 1486.77
#Mann= 17 ,-1 , 0
  4504.4    .035       0  4581.7    .063       0  4668.4    .035       0
  4779.8     .07       0  4832.4     .05       0    5111      .1       0
  5297.9     .05       0  6254.1    .035       0  6428.6     .05       0
  6801.4    .035       0  7281.5     .05       0    8115     .07       0
  8127.5      .1       0  8250.6     .07       0  8299.2      .1       0
  8760.8     .07       0  8999.7      .1       0
#XS Ineff= 2 , 0
                         5192.81         1408.62
Permanent Ineff=
       F       F
#Block Obstruct= 2 , 0
                         6844.31         1408.62
Bank Sta=4832.4,5111
XS Rating Curve= 0 ,0
Exp/Cntr=0.3,0.1

Type RM Length L Ch R = 1 ,1695    ,916,916,916
BEGIN DESCRIPTION:
Cypress Creek 2.0
END DESCRIPTION:
XS GIS Cut Line= 3
      1999353.56     13898535.24      1999353.56     13898035.25
      1999489.83     13894226.97
#Sta/Elev= 30
  4459.5 1419.08  4683.2 1413.79  4781.6 1405.81  4879.6 1378.88  4881.6 1376.38
  5158.2 1378.88  5180.3 1405.22  5283.5 1399.06  5469.9 1402.55  5602.3 1405.02
  5632.2 1405.58  5748.8 1406.17  5961.5 1405.26  6280.7 1404.87  7141.4 1398.16
  7206.9 1399.56  7359.7 1401.65  7430.1 1401.28  7714.7 1398.31  7776.9 1399.99
  7892.5 1381.71    7928 1382.95  7979.5 1382.16  8068.1  1402.4  8147.7 1432.87
  8314.3 1430.99  8566.9  1461.3  8617.5 1477.13  8769.2 1487.47  8770.2 1487.54
#Mann= 19 ,-1 , 0
  4459.5    .035       0  4683.2      .1       0  4781.6     .07       0
  4879.6     .05       0  5158.2      .1       0  5469.9    .035       0
  5602.3     .07       0  5632.2    .035       0  5748.8     .07       0
  5961.5    .035       0  6280.7     .05       0  7141.4    .035       0
  7206.9     .05       0  7359.7    .035       0  7430.1     .05       0
  7714.7     .07       0    7928      .1       0  8566.9     .07       0
  8769.2      .1       0
#Block Obstruct= 2 , 0
                          5703.3         1406.95
Bank Sta=4879.6,5158.2
XS Rating Curve= 0 ,0
Exp/Cntr=0.3,0.1