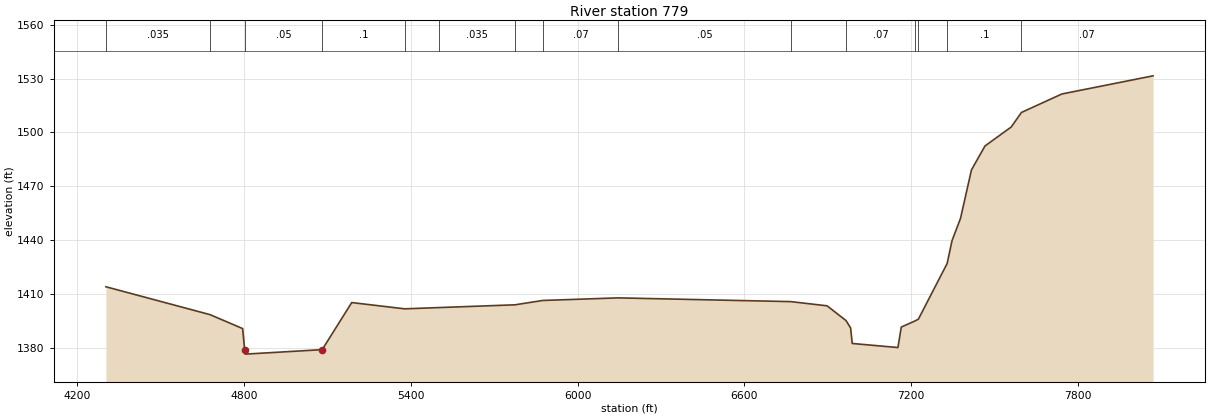
HEC-RAS study Cypress Creek.prj: Cypress Creek Base Level Engineering

--- Cypress Creek.g01 (geometry) --- (continued)

Type RM Length L Ch R = 1 ,779     ,0,0,0
BEGIN DESCRIPTION:
Cypress Creek 1.0
END DESCRIPTION:
XS GIS Cut Line= 4
      1999929.93     13898395.83      2000102.69     13897828.84
      2000224.09     13897101.86      2000614.55     13894698.14
#Sta/Elev= 30
  4304.1 1413.89  4678.3 1398.35  4795.7 1390.57  4803.1 1378.82  4805.2 1376.32
  5081.8 1378.82    5188 1405.07  5378.5 1401.58  5500.2 1402.27  5775.2 1403.82
  5874.4 1406.24  6145.7 1407.69  6766.8  1405.6  6897.1 1403.26  6965.1 1395.05
  6981.6 1390.95  6987.6 1382.26  7151.8 1379.99  7163.9 1391.42  7214.3 1394.89
  7225.6 1395.89  7328.8 1426.87  7346.3 1439.59  7376.7 1451.97  7416.2 1479.05
  7464.8  1492.4    7559 1502.96  7595.9 1511.09  7741.4  1521.4  8069.1 1531.52
#Mann= 15 ,-1 , 0
  4304.1    .035       0  4678.3     .07       0  4803.1     .05       0
  5081.8      .1       0  5378.5     .05       0  5500.2    .035       0
  5775.2     .05       0  5874.4     .07       0  6145.7     .05       0
  6766.8    .035       0  6965.1     .07       0  7214.3      .1       0
  7225.6     .07       0  7328.8      .1       0  7595.9     .07       0
#Block Obstruct= 2 , 0
                          6400.2         1407.78
Bank Sta=4803.1,5081.8
XS Rating Curve= 0 ,0
Exp/Cntr=0.3,0.1

Chan Stop Cuts=-1
Use User Specified Reach Order=0
Composite Channel Slope=5