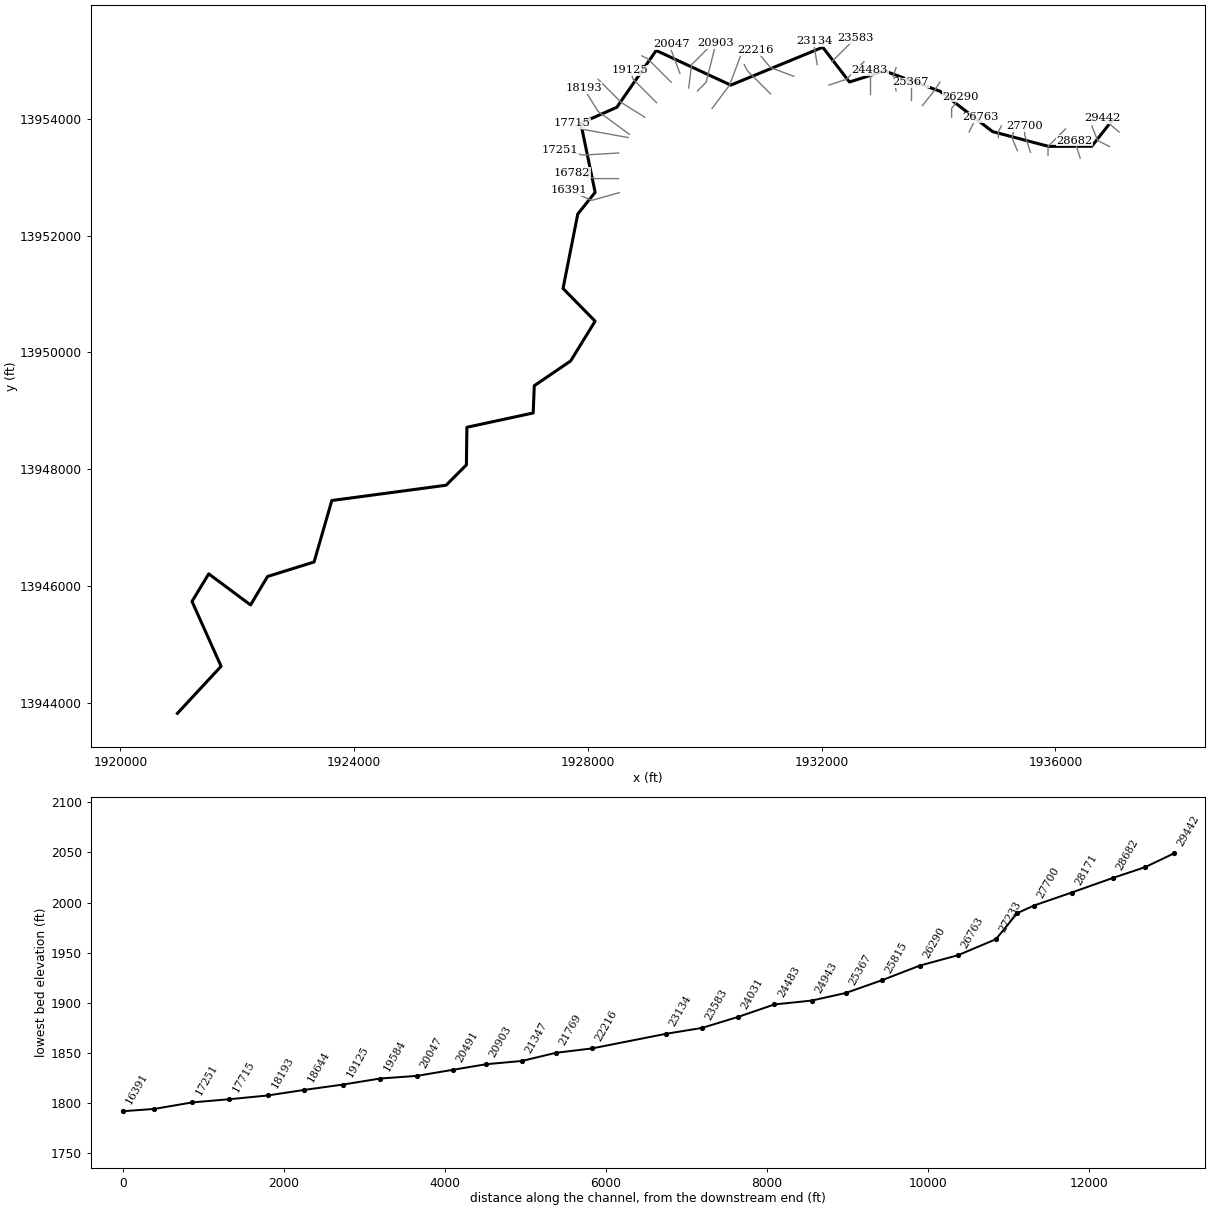
--- East Town Creek.prj (project) ---

Proj Title=East Town Creek Base Level Engineering
Current Plan=p01
Default Exp/Contr=0.3,0.1
English Units
Geom File=g01
Flow File=f01
Plan File=p01
BEGIN DESCRIPTION:
East Town Creek
END DESCRIPTION:

--- East Town Creek.p01 (plan) ---

Plan Title=Multiple Run
Short Identifier=Multiple
Geom File=g01
Flow File=f01
Subcritical Flow
K Sum by GR= 0
Std Step Tol= 0.01
Critical Tol= 0.01
Num of Std Step Trials= 20
Max Error Tol= 0.3
Flow Tol Ratio= 0.001
Split Flow NTrial= 30
Split Flow Tol= 0.02
Split Flow Ratio= 0.02
Log Output Level= 0
Friction Slope Method= 1
Unsteady Friction Slope Method= 2
Unsteady Bridges Friction Slope Method= 1
Parabolic Critical Depth
Global Vel Dist=  1 , 1 , 1
Global Log Level= 0
CheckData=True
Encroach Param= -1, 0, 0, 0
BEGIN DESCRIPTION:
Multiple Run
END DESCRIPTION:

--- East Town Creek.f01 (steady flow) ---

Flow Title=Multiple
Number of Profiles=7
Profile Names=10-year,25-year,50-year,1pct_min,100-year,1pct_plu,500-year
River Rch & RM= East Town Creek,Reach-1,29442
     311     486     639     409     816    1629    1307
River Rch & RM= East Town Creek,Reach-1,27233
    1320    2280    3205    2178    4347    8673    7894
River Rch & RM= East Town Creek,Reach-1,22216
    2384    4245    6091    4216    8412   16784   15855
River Rch & RM= East Town Creek,Reach-1,18644
    3106    5594    8087    5633   11239   22425   21465
River Rch & RM= East Town Creek,Reach-1,15831
    3294    5939    8590    5984   11940   23823   22810
River Rch & RM= East Town Creek,Reach-1,13541
    3655    6613    9586    6690   13348   26633   25594
River Rch & RM= East Town Creek,Reach-1,11107
    4101    7456   10845    7591   15147   30221   29217
River Rch & RM= East Town Creek,Reach-1,9955
    4408    8018   11666    8164   16290   32503   31414
River Rch & RM= East Town Creek,Reach-1,5445
    4542    8253   11998    8387   16735   33390   32201
Boundary for River Rch & Prof#=East Town Creek,Reach-1,1
Up Type=0
Dn Type=3
Dn Slope=0.005
Boundary for River Rch & Prof#=East Town Creek,Reach-1,2
Up Type=0
Dn Type=3
Dn Slope=0.005
Boundary for River Rch & Prof#=East Town Creek,Reach-1,3
Up Type=0
Dn Type=3
Dn Slope=0.005
Boundary for River Rch & Prof#=East Town Creek,Reach-1,4
Up Type=0
Dn Type=3
Dn Slope=0.005
Boundary for River Rch & Prof#=East Town Creek,Reach-1,5
Up Type=0
Dn Type=3
Dn Slope=0.005
Boundary for River Rch & Prof#=East Town Creek,Reach-1,6
Up Type=0
Dn Type=3
Dn Slope=0.005
Boundary for River Rch & Prof#=East Town Creek,Reach-1,7
Up Type=0
Dn Type=3
Dn Slope=0.005

--- East Town Creek.g01 (geometry) ---

Geom Title=Existing Conditions

River Reach=East Town Creek,Reach-1
Reach XY= 30
      1936975.00     13953975.00      1936623.54     13953528.54
      1935885.50     13953526.20      1934926.55     13953778.75
      1934027.43     13954469.48      1933078.32     13954816.96
      1932476.25     13954628.36      1932019.14     13955222.94
      1930445.08     13954574.33      1929168.81     13955167.19
      1928495.09     13954194.78      1927878.54     13953923.54
      1928124.49     13952740.21      1927827.23     13952369.07
      1927575.04     13951095.03      1928124.01     13950535.41
      1927705.23     13949854.87      1927082.80     13949431.21
      1927064.41     13948964.94      1925929.51     13948720.32
      1925921.24     13948076.56      1925573.53     13947728.55
      1923618.16     13947467.20      1923314.24     13946415.27
      1922518.52     13946167.30      1922227.42     13945680.39
      1921511.44     13946212.04      1921225.38     13945740.27
      1921723.11     13944630.71      1920975.00     13943825.00

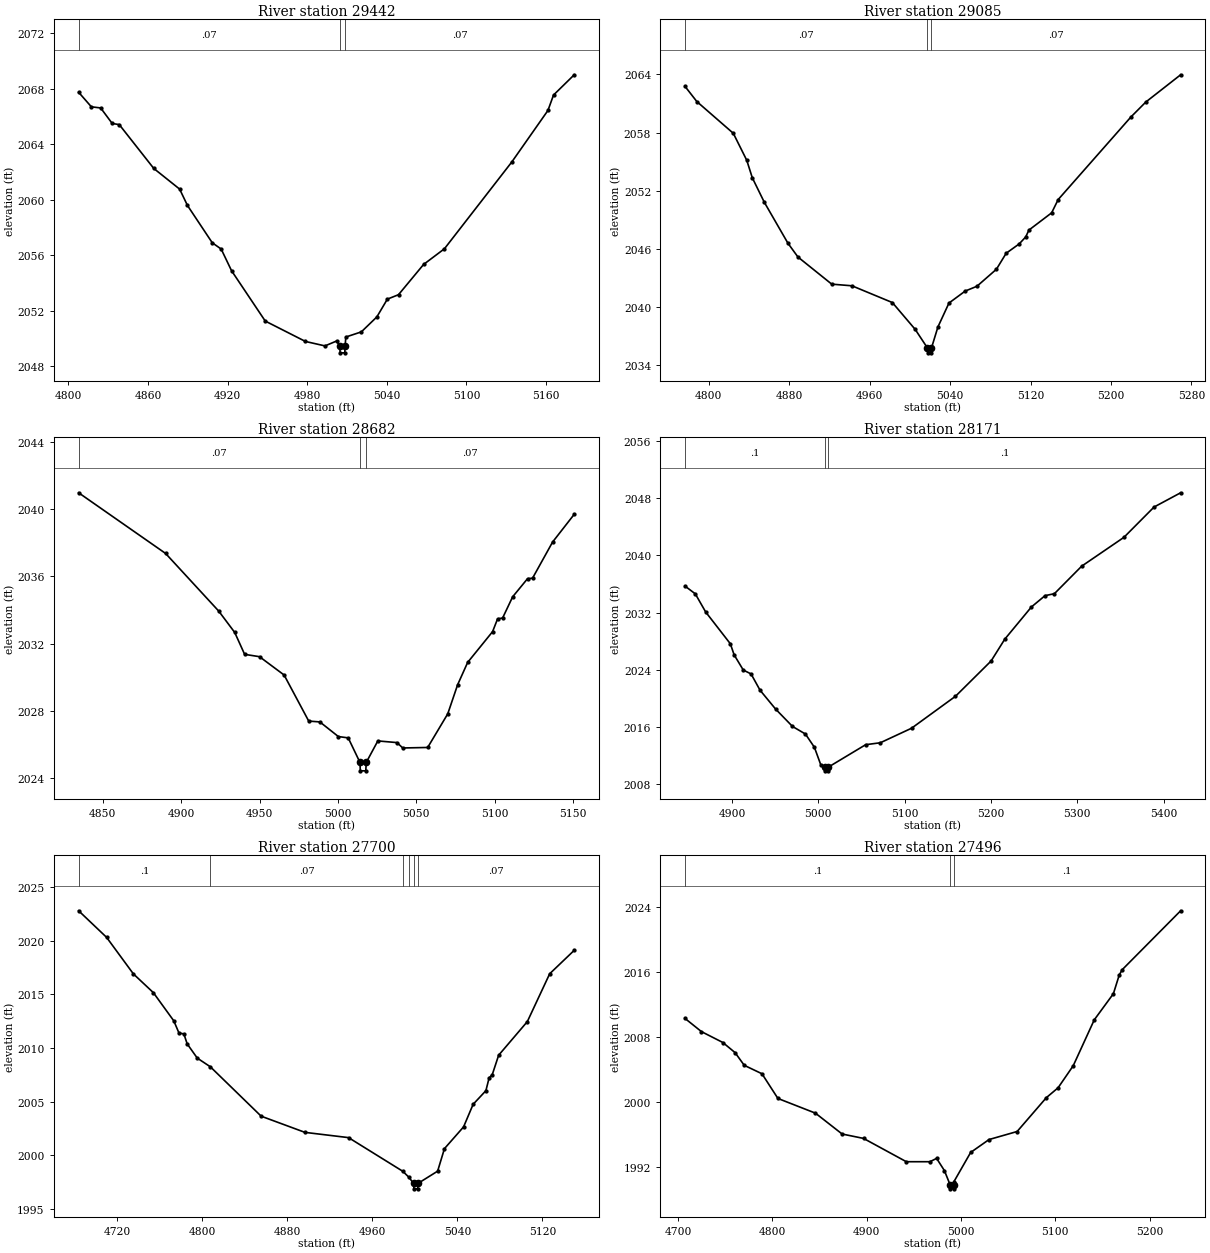
Type RM Length L Ch R = 1,29442,357,357,357
BEGIN DESCRIPTION:
East Town Creek 57.0
END DESCRIPTION:
XS GIS Cut Line= 2
      1937092.95     13953772.29      1936806.52     13954011.85
#Sta/Elev= 30
  4807.8 2067.75  4817.4 2066.70  4824.4 2066.62  4833.1 2065.50  4838.4 2065.42
  4864.4 2062.26  4883.9 2060.77  4889.8 2059.59  4908.5 2056.90  4915.2 2056.45
  4923.0 2054.89  4948.4 2051.26  4978.7 2049.79  4993.4 2049.47  5002.1 2049.82
  5004.6 2049.47  5004.8 2048.97  5008.3 2048.97  5008.6 2049.47  5009.1 2050.11
  5020.8 2050.48  5032.5 2051.56  5040.4 2052.84  5048.8 2053.16  5067.7 2055.34
  5083.4 2056.47  5134.2 2062.73  5161.4 2066.44  5165.6 2067.55  5181.2 2069.01
#Mann=3,-1,0
  4807.8    0.07       0  5004.6    0.05       0  5008.6    0.07       0
Bank Sta=5004.6,5008.6
Exp/Cntr=0.3,0.1

Type RM Length L Ch R = 1,29085,403,403,403
BEGIN DESCRIPTION:
East Town Creek 56.0
END DESCRIPTION:
XS GIS Cut Line= 3
      1936925.02     13953524.99      1936725.00     13953625.00
      1936625.00     13953875.01
#Sta/Elev= 30
  4776.4 2062.76  4788.1 2061.20  4824.4 2057.92  4837.8 2055.13  4843.3 2053.33
  4855.2 2050.81  4878.7 2046.58  4888.7 2045.15  4922.3 2042.35  4942.4 2042.18
  4982.6 2040.45  5005.3 2037.68  5017.5 2035.76  5017.8 2035.26  5021.3 2035.26
  5021.5 2035.76  5027.9 2037.93  5038.9 2040.40  5055.1 2041.64  5066.7 2042.13
  5086.1 2043.89  5095.8 2045.54  5108.7 2046.50  5115.2 2047.22  5118.4 2047.93
  5141.0 2049.71  5147.5 2051.08  5219.9 2059.61  5234.7 2061.15  5269.3 2063.96
#Mann=3,-1,0
  4776.4    0.07       0  5017.5    0.05       0  5021.5    0.07       0
Bank Sta=5017.5,5021.5
Exp/Cntr=0.3,0.1

Type RM Length L Ch R = 1,28682,511,511,511
BEGIN DESCRIPTION:
East Town Creek 55.0
END DESCRIPTION:
XS GIS Cut Line= 3
      1936424.99     13953325.02      1936365.68     13953510.99
      1936325.02     13953624.96
#Sta/Elev= 30
  4834.6 2040.98  4890.1 2037.37  4924.0 2033.94  4934.2 2032.67  4940.5 2031.37
  4950.0 2031.23  4965.7 2030.14  4981.4 2027.40  4988.5 2027.35  5000.3 2026.48
  5006.6 2026.40  5014.1 2024.94  5014.3 2024.44  5017.8 2024.44  5018.1 2024.94
  5025.5 2026.22  5037.7 2026.12  5041.4 2025.80  5057.3 2025.83  5070.1 2027.83
  5076.4 2029.56  5082.8 2030.89  5098.7 2032.72  5101.9 2033.48  5105.1 2033.53
  5111.5 2034.79  5121.0 2035.87  5124.2 2035.90  5137.0 2038.05  5150.8 2039.70
#Mann=3,-1,0
  4834.6    0.07       0  5014.1    0.05       0  5018.1    0.07       0
Bank Sta=5014.1,5018.1
Exp/Cntr=0.3,0.1

Type RM Length L Ch R = 1,28171,471,471,471
BEGIN DESCRIPTION:
East Town Creek 54.0
END DESCRIPTION:
XS GIS Cut Line= 3
      1935875.00     13953375.00      1935875.00     13953525.00
      1936175.03     13953825.03
#Sta/Elev= 30
  4845.5 2035.69  4857.4 2034.61  4869.4 2032.08  4898.0 2027.64  4902.4 2026.09
  4913.0 2023.97  4922.0 2023.43  4932.4 2021.16  4950.4 2018.53  4970.0 2016.10
  4985.0 2015.04  4995.4 2013.19  5002.9 2010.71  5007.3 2010.40  5007.5 2009.90
  5011.0 2009.90  5011.3 2010.40  5054.8 2013.55  5071.8 2013.82  5108.0 2015.85
  5158.9 2020.31  5200.2 2025.24  5216.0 2028.28  5246.9 2032.78  5262.7 2034.36
  5273.5 2034.63  5305.1 2038.47  5354.1 2042.50  5389.0 2046.73  5419.8 2048.72
#Mann=3,-1,0
  4845.5     0.1       0  5007.3    0.05       0  5011.3     0.1       0
Bank Sta=5007.3,5011.3
Exp/Cntr=0.3,0.1

Type RM Length L Ch R = 1,27700,204,204,204
BEGIN DESCRIPTION:
East Town Creek 53.0
END DESCRIPTION:
XS GIS Cut Line= 3
      1935574.99     13953425.02      1935475.00     13953725.00
      1935475.00     13953874.99
#Sta/Elev= 30
  4683.7 2022.80  4710.0 2020.32  4735.2 2016.91  4754.0 2015.16  4773.2 2012.53
  4778.1 2011.39  4782.7 2011.31  4785.8 2010.38  4795.3 2009.05  4807.6 2008.24
  4855.4 2003.63  4896.6 2002.12  4937.6 2001.63  4988.6 1998.49  4994.4 1997.93
  4998.8 1997.35  4999.1 1996.85  5002.6 1996.85  5002.8 1997.35  5021.4 1998.50
  5027.8 2000.60  5045.8 2002.63  5054.8 2004.74  5066.8 2006.01  5069.8 2007.19
  5072.8 2007.51  5078.8 2009.32  5105.8 2012.46  5126.8 2016.92  5149.9 2019.11
#Mann=6,-1,0
  4683.7     0.1       0  4807.6    0.07       0  4988.6     0.1       0
  4994.4    0.07       0  4998.8    0.05       0  5002.8    0.07       0
Bank Sta=4998.8,5002.8
Exp/Cntr=0.3,0.1

Type RM Length L Ch R = 1,27496,263,263,263
BEGIN DESCRIPTION:
Mapping XS af0a3574
END DESCRIPTION:
XS GIS Cut Line= 3
      1935350.22     13953451.87      1935258.96     13953673.41
      1935326.98     13953951.20
#Sta/Elev= 30
  4707.4 2010.31  4724.8 2008.69  4747.5 2007.35  4760.5 2006.10  4770.2 2004.54
  4789.0 2003.50  4805.9 2000.46  4845.7 1998.65  4874.0 1996.08  4896.7 1995.54
  4942.1 1992.67  4967.1 1992.67  4974.2 1993.08  4982.5 1991.57  4988.5 1989.83
  4988.8 1989.33  4992.3 1989.33  4992.5 1989.83  4992.6 1990.22  5010.3 1993.81
  5029.8 1995.40  5059.6 1996.39  5090.6 2000.56  5103.0 2001.77  5119.1 2004.49
  5141.4 2010.14  5161.7 2013.36  5167.8 2015.63  5170.9 2016.30  5233.0 2023.57
#Mann=3,-1,0
  4707.4     0.1       0  4988.5    0.05       0  4992.5     0.1       0
Bank Sta=4988.5,4992.5
Exp/Cntr=0.3,0.1

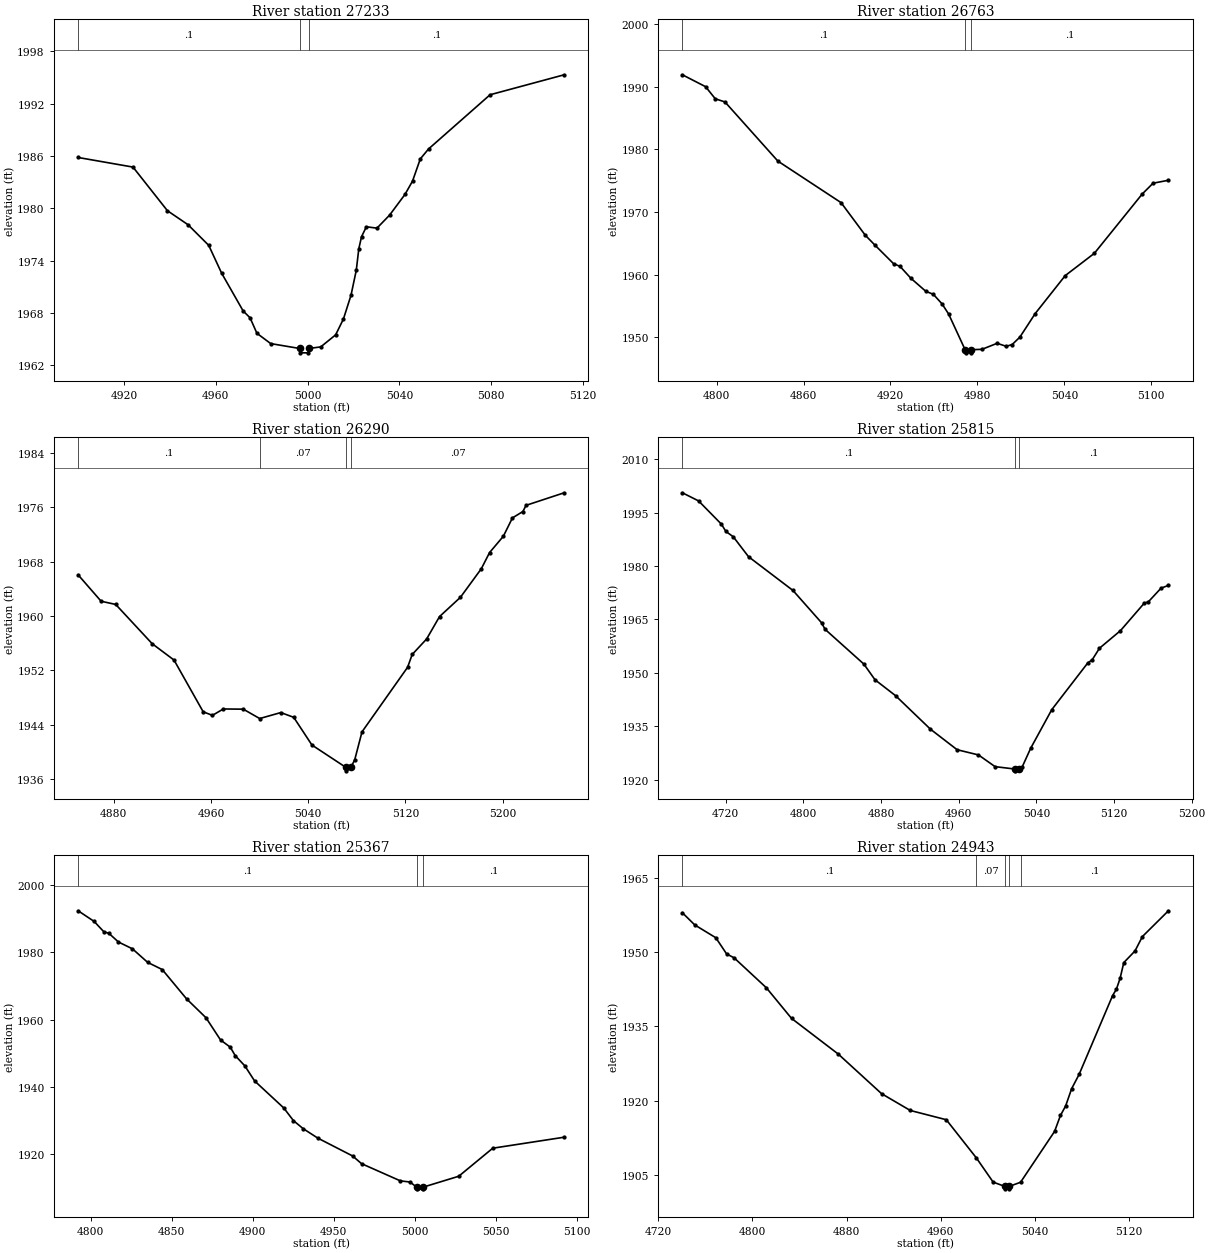
Type RM Length L Ch R = 1,27233,470,470,470
BEGIN DESCRIPTION:
East Town Creek 52.0
END DESCRIPTION:
XS GIS Cut Line= 3
      1935025.00     13953675.00      1935025.00     13953775.00
      1935075.00     13953875.00
#Sta/Elev= 30
  4900.0 1985.83  4923.9 1984.73  4938.9 1979.73  4947.9 1978.12  4956.9 1975.76
  4962.5 1972.58  4971.9 1968.24  4974.9 1967.46  4977.9 1965.68  4983.9 1964.50
  4996.5 1963.94  4996.7 1963.44  5000.2 1963.44  5000.5 1963.94  5005.7 1964.12
  5012.2 1965.50  5015.6 1967.32  5018.9 1970.04  5021.2 1972.91  5022.3 1975.38
  5023.5 1976.76  5025.6 1977.89  5030.2 1977.73  5035.7 1979.22  5042.4 1981.59
  5045.7 1983.12  5049.1 1985.67  5052.7 1986.81  5079.5 1993.02  5111.8 1995.31
#Mann=3,-1,0
  4900.0     0.1       0  4996.5    0.05       0  5000.5     0.1       0
Bank Sta=4996.5,5000.5
Exp/Cntr=0.3,0.1

Type RM Length L Ch R = 1,26763,473,473,473
BEGIN DESCRIPTION:
East Town Creek 51.0
END DESCRIPTION:
XS GIS Cut Line= 3
      1934525.01     13953775.01      1934625.00     13953975.00
      1934725.00     13954025.00
#Sta/Elev= 30
  4776.4 1991.89  4792.4 1989.99  4799.1 1988.06  4805.8 1987.55  4842.3 1978.11
  4885.9 1971.48  4902.6 1966.28  4909.3 1964.69  4922.1 1961.74  4926.6 1961.30
  4934.1 1959.40  4944.4 1957.32  4949.6 1956.84  4955.6 1955.31  4960.1 1953.71
  4971.5 1948.00  4971.8 1947.50  4975.3 1947.50  4975.5 1948.00  4983.1 1948.06
  4993.6 1949.02  4999.9 1948.54  5004.0 1948.83  5009.3 1950.01  5019.9 1953.78
  5040.6 1959.83  5060.7 1963.39  5093.7 1972.85  5101.2 1974.58  5111.8 1975.05
#Mann=3,-1,0
  4776.4     0.1       0  4971.5    0.05       0  4975.5     0.1       0
Bank Sta=4971.5,4975.5
Exp/Cntr=0.3,0.1

Type RM Length L Ch R = 1,26290,475,475,475
BEGIN DESCRIPTION:
East Town Creek 50.0
END DESCRIPTION:
XS GIS Cut Line= 3
      1934225.00     13954025.01      1934225.00     13954175.00
      1934375.01     13954375.01
#Sta/Elev= 30
  4850.7 1966.04  4869.6 1962.16  4881.6 1961.69  4911.6 1955.91  4929.6 1953.50
  4953.6 1945.88  4961.2 1945.36  4970.2 1946.30  4986.6 1946.27  5000.1 1944.89
  5017.5 1945.77  5028.1 1945.07  5043.1 1940.99  5071.1 1937.69  5071.3 1937.19
  5075.1 1937.69  5078.3 1938.81  5084.3 1942.93  5121.8 1952.43  5125.6 1954.32
  5137.5 1956.61  5148.1 1959.90  5165.3 1962.74  5182.5 1966.95  5189.3 1969.33
  5200.6 1971.72  5208.1 1974.43  5216.7 1975.37  5219.3 1976.28  5250.7 1978.13
#Mann=4,-1,0
  4850.7     0.1       0  5000.1    0.07       0  5071.1    0.05       0
  5075.1    0.07       0
Bank Sta=5071.1,5075.1
Exp/Cntr=0.3,0.1

Type RM Length L Ch R = 1,25815,448,448,448
BEGIN DESCRIPTION:
East Town Creek 49.0
END DESCRIPTION:
XS GIS Cut Line= 3
      1933724.98     13954224.98      1933925.00     13954475.00
      1934025.02     13954625.03
#Sta/Elev= 30
  4675.5 2000.62  4692.2 1998.33  4715.7 1991.79  4720.3 1989.74  4727.9 1988.26
  4743.6 1982.65  4789.4 1973.15  4818.8 1964.08  4822.4 1962.24  4862.4 1952.45
  4873.9 1948.03  4895.0 1943.58  4930.9 1934.16  4958.4 1928.38  4980.4 1926.91
  4997.5 1923.62  5018.1 1922.94  5018.4 1922.44  5022.1 1922.94  5025.6 1923.65
  5034.2 1928.81  5055.9 1939.65  5092.7 1952.69  5097.7 1953.74  5105.0 1956.91
  5126.6 1961.85  5151.1 1969.58  5155.3 1969.95  5168.4 1973.80  5176.0 1974.58
#Mann=3,-1,0
  4675.5     0.1       0  5018.1    0.05       0  5022.1     0.1       0
Bank Sta=5018.1,5022.1
Exp/Cntr=0.3,0.1

Type RM Length L Ch R = 1,25367,424,424,424
BEGIN DESCRIPTION:
East Town Creek 48.0
END DESCRIPTION:
XS GIS Cut Line= 3
      1933525.00     13954325.00      1933525.00     13954525.00
      1933525.00     13954625.00
#Sta/Elev= 30
  4792.2 1992.25  4802.1 1989.08  4808.1 1986.00  4811.1 1985.59  4817.1 1982.98
  4825.7 1980.97  4835.1 1976.95  4844.1 1974.82  4859.1 1966.14  4871.1 1960.53
  4880.1 1953.93  4886.1 1951.80  4889.1 1949.32  4895.1 1946.25  4901.1 1941.79
  4919.1 1933.78  4925.1 1930.01  4931.1 1927.63  4940.1 1924.84  4961.6 1919.54
  4967.1 1917.26  4991.1 1912.15  4997.1 1911.81  5001.1 1910.29  5001.4 1909.79
  5004.9 1909.79  5005.1 1910.29  5027.1 1913.52  5048.1 1921.84  5092.2 1925.10
#Mann=3,-1,0
  4792.2     0.1       0  5001.1    0.05       0  5005.1     0.1       0
Bank Sta=5001.1,5005.1
Exp/Cntr=0.3,0.1

Type RM Length L Ch R = 1,24943,460,460,460
BEGIN DESCRIPTION:
East Town Creek 47.0
END DESCRIPTION:
XS GIS Cut Line= 3
      1933274.99     13954475.04      1933225.00     13954725.00
      1933274.96     13954874.88
#Sta/Elev= 30
  4740.5 1957.90  4751.0 1955.45  4768.9 1952.86  4778.1 1949.59  4784.4 1948.82
  4811.8 1942.78  4833.2 1936.60  4873.0 1929.38  4909.7 1921.41  4934.1 1918.02
  4964.7 1916.15  4990.3 1908.43  5004.5 1903.57  5014.3 1902.71  5014.6 1902.21
  5018.1 1902.21  5018.3 1902.71  5027.8 1903.54  5056.7 1913.80  5061.7 1917.02
  5066.1 1918.94  5071.2 1922.42  5077.5 1925.28  5106.0 1941.20  5109.2 1942.47
  5112.3 1944.64  5115.5 1947.85  5125.0 1950.19  5131.3 1953.10  5153.4 1958.30
#Mann=5,-1,0
  4740.5     0.1       0  4990.3    0.07       0  5014.3    0.05       0
  5018.3    0.07       0  5027.8     0.1       0
Bank Sta=5014.3,5018.3
Exp/Cntr=0.3,0.1

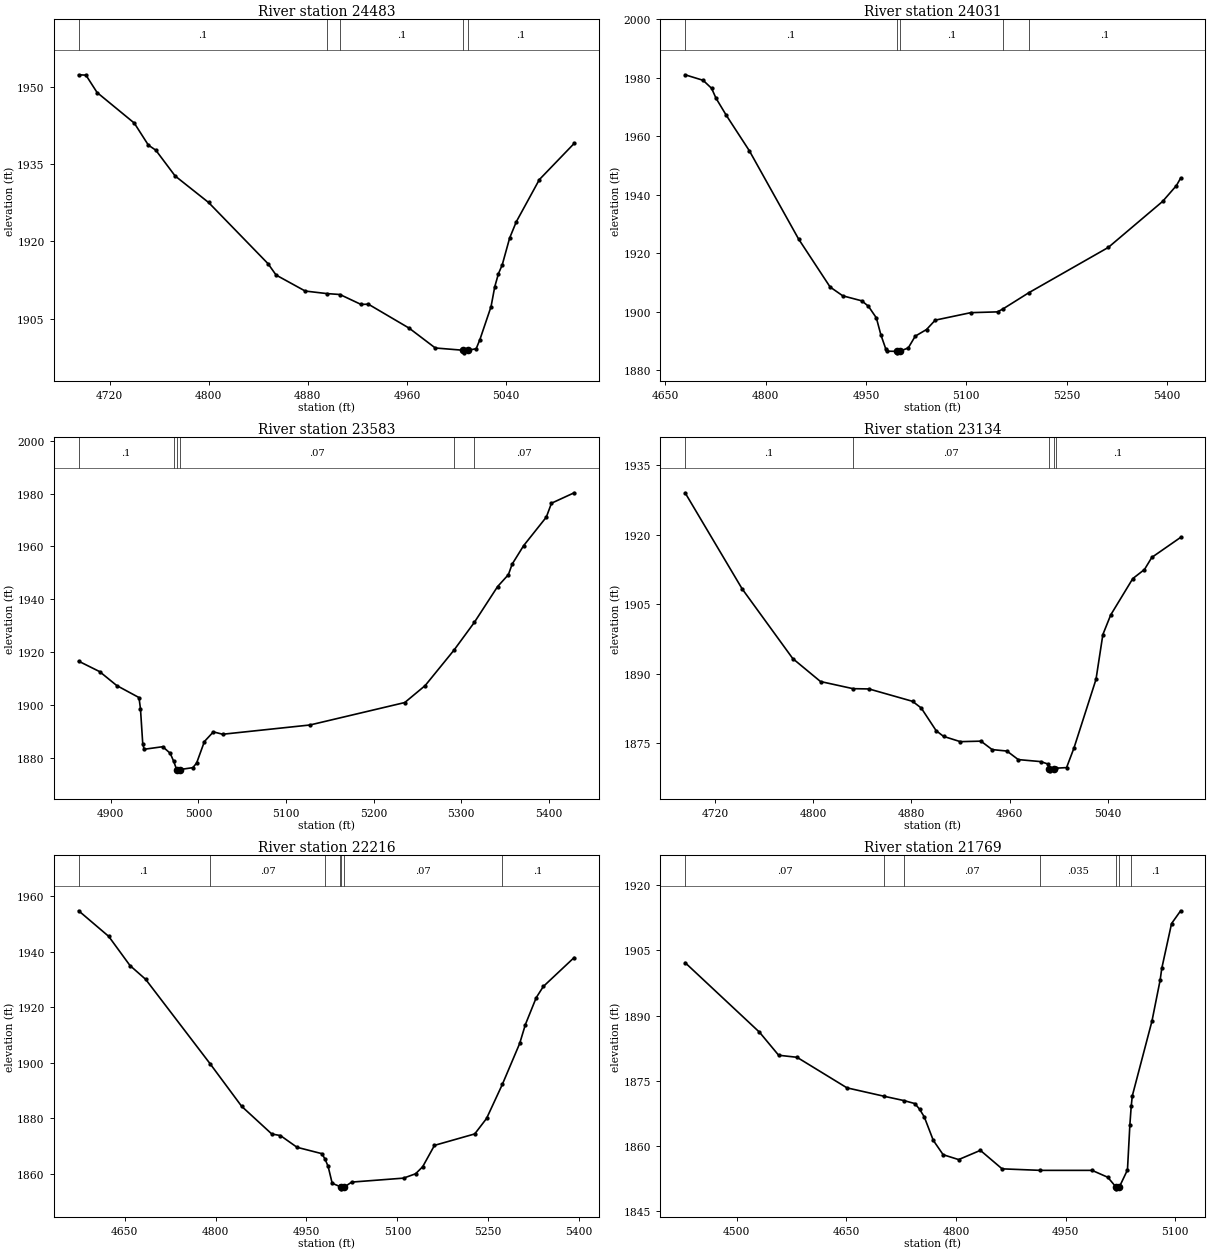
Type RM Length L Ch R = 1,24483,452,452,452
BEGIN DESCRIPTION:
East Town Creek 46.0
END DESCRIPTION:
XS GIS Cut Line= 3
      1932825.00     13954425.04      1932825.00     13954725.00
      1932825.00     13954825.04
#Sta/Elev= 30
  4695.0 1952.31  4700.9 1952.24  4709.9 1948.87  4739.9 1942.95  4751.3 1938.67
  4757.3 1937.69  4772.9 1932.69  4799.9 1927.55  4847.9 1915.68  4854.4 1913.48
  4877.9 1910.38  4895.3 1909.89  4905.9 1909.71  4922.9 1907.79  4928.9 1907.83
  4961.9 1903.17  4982.9 1899.34  5005.4 1898.90  5005.7 1898.40  5009.4 1898.90
  5015.9 1899.20  5018.9 1900.97  5027.9 1907.36  5030.9 1911.22  5033.9 1913.77
  5036.9 1915.43  5042.9 1920.65  5048.3 1923.82  5066.9 1931.99  5095.0 1939.00
#Mann=5,-1,0
  4695.0     0.1       0  4895.3    0.07       0  4905.9     0.1       0
  5005.4    0.05       0  5009.4     0.1       0
Bank Sta=5005.4,5009.4
Exp/Cntr=0.3,0.1

Type RM Length L Ch R = 1,24031,448,448,448
BEGIN DESCRIPTION:
East Town Creek 45.0
END DESCRIPTION:
XS GIS Cut Line= 3
      1932125.02     13954575.01      1932425.00     13954675.00
      1932725.02     13954975.02
#Sta/Elev= 30
  4679.7 1981.03  4706.6 1979.14  4719.3 1976.40  4725.9 1973.01  4741.4 1967.12
  4775.7 1955.05  4849.2 1924.90  4896.4 1908.45  4915.3 1905.44  4943.8 1903.72
  4953.6 1901.88  4965.5 1897.90  4972.2 1892.14  4979.7 1887.19  4981.7 1886.51
  4996.1 1886.44  4996.4 1885.94  5000.1 1886.44  5013.2 1887.63  5023.6 1891.64
  5040.5 1893.92  5053.5 1897.12  5106.6 1899.68  5146.6 1899.95  5155.1 1901.01
  5193.2 1906.48  5312.1 1921.99  5393.2 1937.71  5413.9 1943.14  5420.2 1945.70
#Mann=5,-1,0
  4679.7     0.1       0  4996.1    0.05       0  5000.1     0.1       0
  5155.1    0.07       0  5193.2     0.1       0
Bank Sta=4996.1,5000.1
Exp/Cntr=0.3,0.1

Type RM Length L Ch R = 1,23583,449,449,449
BEGIN DESCRIPTION:
East Town Creek 44.0
END DESCRIPTION:
XS GIS Cut Line= 3
      1932175.01     13954975.01      1932275.00     13955075.00
      1932575.02     13955375.02
#Sta/Elev= 30
  4863.2 1916.51  4887.1 1912.57  4906.7 1907.28  4932.1 1902.73  4933.8 1898.47
  4936.4 1885.18  4938.0 1883.14  4959.2 1884.11  4967.7 1881.64  4971.6 1878.67
  4975.1 1875.47  4975.4 1874.97  4979.1 1875.47  4993.6 1876.18  4997.9 1877.93
  5006.8 1886.08  5017.0 1889.73  5027.6 1888.83  5127.3 1892.34  5235.5 1900.84
  5258.8 1907.27  5291.7 1920.69  5314.9 1931.19  5341.5 1944.78  5353.8 1949.28
  5358.1 1953.27  5371.2 1960.27  5397.1 1971.08  5403.0 1976.35  5428.9 1980.30
#Mann=6,-1,0
  4863.2     0.1       0  4971.6    0.07       0  4975.1    0.05       0
  4979.1    0.07       0  5291.7     0.1       0  5314.9    0.07       0
Bank Sta=4975.1,4979.1
Exp/Cntr=0.3,0.1

Type RM Length L Ch R = 1,23134,918,918,918
BEGIN DESCRIPTION:
East Town Creek 43.0
END DESCRIPTION:
XS GIS Cut Line= 3
      1931924.99     13954925.05      1931875.00     13955225.00
      1931875.00     13955324.91
#Sta/Elev= 30
  4695.5 1929.11  4742.0 1908.37  4783.3 1893.31  4805.9 1888.36  4832.4 1886.82
  4845.4 1886.76  4880.9 1884.09  4888.0 1882.65  4900.2 1877.74  4906.2 1876.52
  4919.9 1875.38  4936.7 1875.49  4945.8 1873.67  4957.9 1873.35  4967.1 1871.51
  4985.6 1871.07  4991.4 1870.54  4992.4 1869.58  4992.7 1869.08  4996.4 1869.58
  4997.8 1869.65  5006.5 1869.78  5012.5 1873.98  5030.5 1888.83  5036.1 1898.51
  5042.5 1902.74  5060.5 1910.59  5070.0 1912.54  5076.0 1915.16  5099.5 1919.48
#Mann=5,-1,0
  4695.5     0.1       0  4832.4    0.07       0  4992.4    0.05       0
  4996.4    0.07       0  4997.8     0.1       0
Bank Sta=4992.4,4996.4
Exp/Cntr=0.3,0.1

Type RM Length L Ch R = 1,22216,447,447,447
BEGIN DESCRIPTION:
East Town Creek 42.0
END DESCRIPTION:
XS GIS Cut Line= 3
      1931525.00     13954725.00      1931125.00     13954875.00
      1930875.01     13955174.99
#Sta/Elev= 30
  4574.0 1954.78  4623.6 1945.56  4658.8 1935.02  4684.5 1930.08  4790.7 1899.69
  4843.0 1884.27  4892.7 1874.29  4907.0 1873.72  4934.4 1869.49  4975.3 1867.20
  4980.6 1865.25  4985.7 1862.59  4992.4 1856.51  5004.8 1855.38  5006.3 1855.01
  5006.7 1854.51  5011.5 1855.01  5024.5 1856.94  5110.1 1858.37  5130.0 1859.94
  5141.7 1862.48  5161.2 1870.19  5227.6 1874.31  5247.1 1879.88  5273.2 1892.19
  5301.8 1906.94  5311.2 1913.76  5329.1 1923.46  5340.8 1927.48  5391.7 1937.92
#Mann=7,-1,0
  4574.0     0.1       0  4790.7    0.07       0  4980.6   0.035       0
  5004.8    0.07       0  5006.3   0.035       0  5011.5    0.07       0
  5273.2     0.1       0
Bank Sta=5006.3,5011.5
Exp/Cntr=0.3,0.1

Type RM Length L Ch R = 1,21769,422,422,422
BEGIN DESCRIPTION:
East Town Creek 41.0
END DESCRIPTION:
XS GIS Cut Line= 3
      1931125.01     13954424.99      1930725.00     13954825.00
      1930675.00     13954925.00
#Sta/Elev= 30
  4429.7 1902.19  4531.4 1886.19  4557.6 1880.89  4582.7 1880.42  4651.0 1873.39
  4701.9 1871.45  4728.7 1870.47  4743.9 1869.77  4750.3 1868.47  4756.7 1866.71
  4769.0 1861.32  4782.5 1858.01  4803.7 1856.89  4833.4 1859.01  4863.1 1854.76
  4915.6 1854.41  4986.1 1854.41  5007.6 1852.82  5018.4 1850.66  5018.8 1850.16
  5023.6 1850.66  5034.5 1854.51  5037.8 1864.90  5039.6 1869.12  5041.1 1871.53
  5068.0 1888.75  5079.2 1898.20  5081.4 1900.87  5094.8 1911.19  5107.2 1914.12
#Mann=7,-1,0
  4429.7    0.07       0  4701.9     0.1       0  4728.7    0.07       0
  4915.6   0.035       0  5018.4   0.035       0  5023.6   0.035       0
  5039.6     0.1       0
Bank Sta=5018.4,5023.6
Exp/Cntr=0.3,0.1

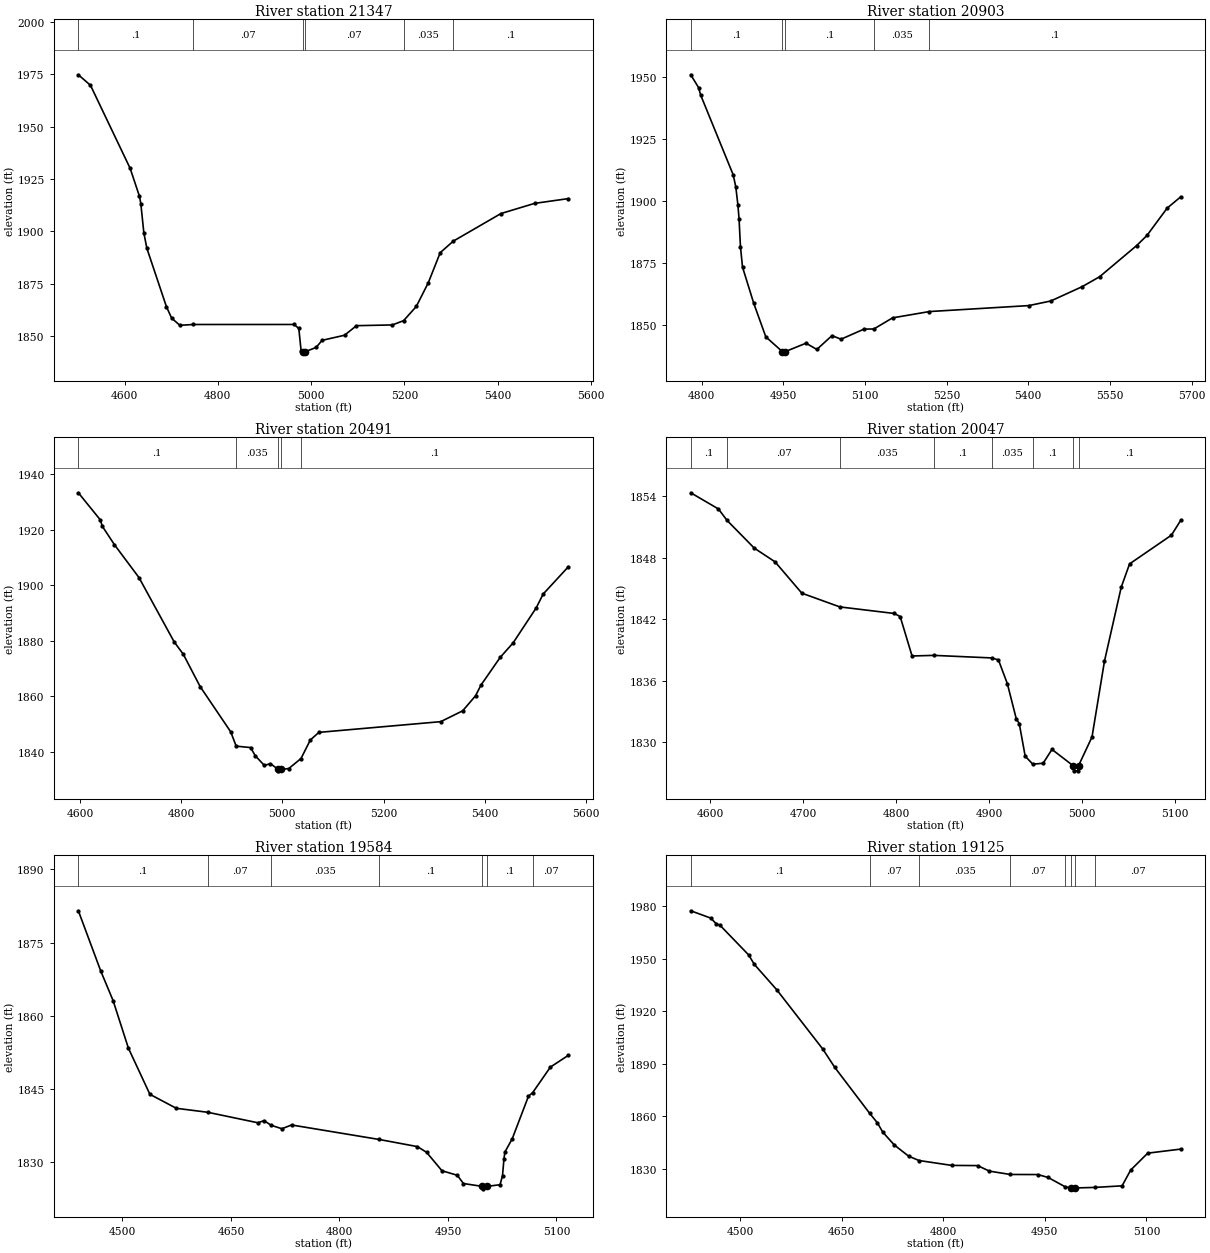
Type RM Length L Ch R = 1,21347,444,444,444
BEGIN DESCRIPTION:
East Town Creek 40.0
END DESCRIPTION:
XS GIS Cut Line= 3
      1930124.98     13954174.97      1930425.00     13954575.00
      1930618.70     13955090.04
#Sta/Elev= 30
  4501.0 1974.77  4527.0 1969.74  4612.0 1930.10  4632.0 1916.73  4634.9 1913.21
  4641.4 1899.26  4647.8 1891.96  4689.7 1864.10  4700.9 1858.61  4718.5 1855.17
  4747.2 1855.56  4963.4 1855.57  4973.5 1853.66  4978.4 1843.02  4981.6 1842.53
  4982.0 1842.03  4986.8 1842.53  5010.6 1844.61  5023.4 1848.00  5071.5 1850.43
  5097.1 1855.00  5174.0 1855.35  5198.1 1857.39  5225.3 1864.16  5251.0 1875.48
  5276.6 1889.86  5304.5 1895.34  5406.7 1908.52  5478.9 1913.38  5551.3 1915.66
#Mann=6,-1,0
  4501.0     0.1       0  4747.2    0.07       0  4981.6    0.05       0
  4986.8    0.07       0  5198.1   0.035       0  5304.5     0.1       0
Bank Sta=4981.6,4986.8
Exp/Cntr=0.3,0.1

Type RM Length L Ch R = 1,20903,412,412,412
BEGIN DESCRIPTION:
East Town Creek 39.0
END DESCRIPTION:
XS GIS Cut Line= 3
      1929875.02     13954475.02      1930025.00     13954625.00
      1930191.16     13955292.63
#Sta/Elev= 30
  4780.0 1950.70  4794.4 1945.54  4798.2 1942.54  4858.1 1910.36  4862.8 1905.45
  4866.6 1898.33  4868.7 1892.80  4871.3 1881.49  4875.1 1873.28  4895.8 1858.66
  4917.9 1845.21  4948.2 1839.28  4948.7 1838.78  4953.7 1839.28  4991.7 1842.66
  5011.6 1840.14  5039.4 1845.71  5056.0 1844.26  5098.2 1848.33  5116.3 1848.38
  5150.7 1852.86  5218.5 1855.40  5401.1 1857.80  5441.3 1859.65  5499.1 1865.43
  5531.0 1869.41  5599.0 1881.95  5618.0 1886.04  5655.1 1897.04  5680.1 1901.59
#Mann=5,-1,0
  4780.0     0.1       0  4948.2    0.05       0  4953.7     0.1       0
  5116.3   0.035       0  5218.5     0.1       0
Bank Sta=4948.2,4953.7
Exp/Cntr=0.3,0.1

Type RM Length L Ch R = 1,20491,444,444,444
BEGIN DESCRIPTION:
East Town Creek 38.0
END DESCRIPTION:
XS GIS Cut Line= 3
      1929725.00     13954525.04      1929775.00     13954925.00
      1930175.03     13955325.03
#Sta/Elev= 30
  4596.7 1933.34  4640.1 1923.58  4643.9 1921.33  4668.1 1914.63  4716.5 1902.82
  4786.0 1879.69  4804.2 1875.19  4837.4 1863.58  4897.9 1847.27  4908.7 1842.11
  4937.2 1841.60  4946.4 1838.66  4964.4 1835.17  4976.5 1835.80  4991.9 1833.72
  4992.3 1833.22  4997.5 1833.72  5012.8 1834.06  5036.9 1837.66  5055.3 1844.33
  5072.2 1847.07  5313.1 1850.93  5356.5 1854.83  5381.9 1860.24  5392.6 1864.08
  5430.7 1874.08  5456.2 1879.29  5501.7 1891.85  5515.6 1896.87  5565.5 1906.72
#Mann=5,-1,0
  4596.7     0.1       0  4908.7   0.035       0  4991.9   0.035       0
  4997.5   0.035       0  5036.9     0.1       0
Bank Sta=4991.9,4997.5
Exp/Cntr=0.3,0.1

Type RM Length L Ch R = 1,20047,463,463,463
BEGIN DESCRIPTION:
East Town Creek 37.0
END DESCRIPTION:
XS GIS Cut Line= 3
      1929575.00     13954774.99      1929425.00     13955175.00
      1929425.00     13955274.99
#Sta/Elev= 30
  4578.8 1854.35  4608.6 1852.77  4617.9 1851.65  4647.1 1848.95  4669.5 1847.61
  4698.3 1844.55  4739.2 1843.21  4797.7 1842.57  4804.1 1842.27  4816.9 1838.42
  4840.4 1838.48  4902.5 1838.23  4909.8 1838.04  4919.4 1835.72  4929.0 1832.29
  4932.2 1831.83  4938.6 1828.64  4946.8 1827.86  4957.9 1827.95  4967.4 1829.30
  4990.2 1827.71  4990.7 1827.21  4995.5 1827.21  4996.0 1827.71  5010.5 1830.52
  5023.9 1837.92  5041.9 1845.13  5050.9 1847.41  5095.9 1850.21  5106.0 1851.67
#Mann=8,-1,0
  4578.8     0.1       0  4617.9    0.07       0  4739.2   0.035       0
  4840.4     0.1       0  4902.5   0.035       0  4946.8     0.1       0
  4990.2    0.05       0  4996.0     0.1       0
Bank Sta=4990.2,4996
Exp/Cntr=0.3,0.1

Type RM Length L Ch R = 1,19584,459,459,459
BEGIN DESCRIPTION:
East Town Creek 36.0
END DESCRIPTION:
XS GIS Cut Line= 3
      1929425.04     13954624.96      1929025.00     13955025.00
      1928925.03     13955074.98
#Sta/Elev= 30
  4439.1 1881.52  4470.1 1869.15  4487.1 1863.11  4508.3 1853.34  4538.0 1843.88
  4574.5 1841.01  4618.1 1840.19  4687.3 1838.04  4695.8 1838.48  4705.5 1837.53
  4720.5 1836.82  4733.9 1837.59  4855.2 1834.61  4907.9 1833.15  4920.6 1831.97
  4941.8 1828.20  4963.0 1827.27  4971.5 1825.58  4997.6 1824.99  4998.0 1824.49
  5003.4 1824.99  5022.1 1825.33  5025.5 1827.20  5027.5 1830.61  5028.8 1832.04
  5038.9 1834.74  5061.4 1843.49  5067.3 1844.24  5091.7 1849.46  5116.6 1851.88
#Mann=7,-1,0
  4439.1     0.1       0  4618.1    0.07       0  4705.5   0.035       0
  4855.2     0.1       0  4997.6    0.05       0  5003.4     0.1       0
  5067.3    0.07       0
Bank Sta=4997.6,5003.4
Exp/Cntr=0.3,0.1

Type RM Length L Ch R = 1,19125,481,481,481
BEGIN DESCRIPTION:
East Town Creek 35.0
END DESCRIPTION:
XS GIS Cut Line= 3
      1929174.98     13954275.02      1928775.00     13954675.00
      1928724.99     13954825.03
#Sta/Elev= 30
  4427.0 1977.37  4456.6 1973.18  4465.0 1969.78  4470.0 1969.18  4512.5 1952.15
  4520.9 1946.75  4554.1 1932.20  4622.0 1898.37  4639.7 1887.89  4691.4 1861.57
  4702.6 1856.25  4710.6 1850.90  4727.6 1843.57  4748.8 1837.16  4764.1 1834.68
  4812.5 1831.88  4850.7 1831.77  4868.0 1828.62  4898.9 1826.70  4939.7 1826.65
  4954.8 1825.00  4979.5 1819.76  4988.1 1818.99  4988.6 1818.49  4994.0 1818.99
  5023.9 1819.30  5064.1 1820.21  5076.8 1829.23  5102.0 1838.88  5150.8 1841.20
#Mann=8,-1,0
  4427.0     0.1       0  4691.4    0.07       0  4764.1   0.035       0
  4898.9    0.07       0  4979.5   0.035       0  4988.1   0.035       0
  4994.0   0.035       0  5023.9    0.07       0
Bank Sta=4988.1,4994
Exp/Cntr=0.3,0.1

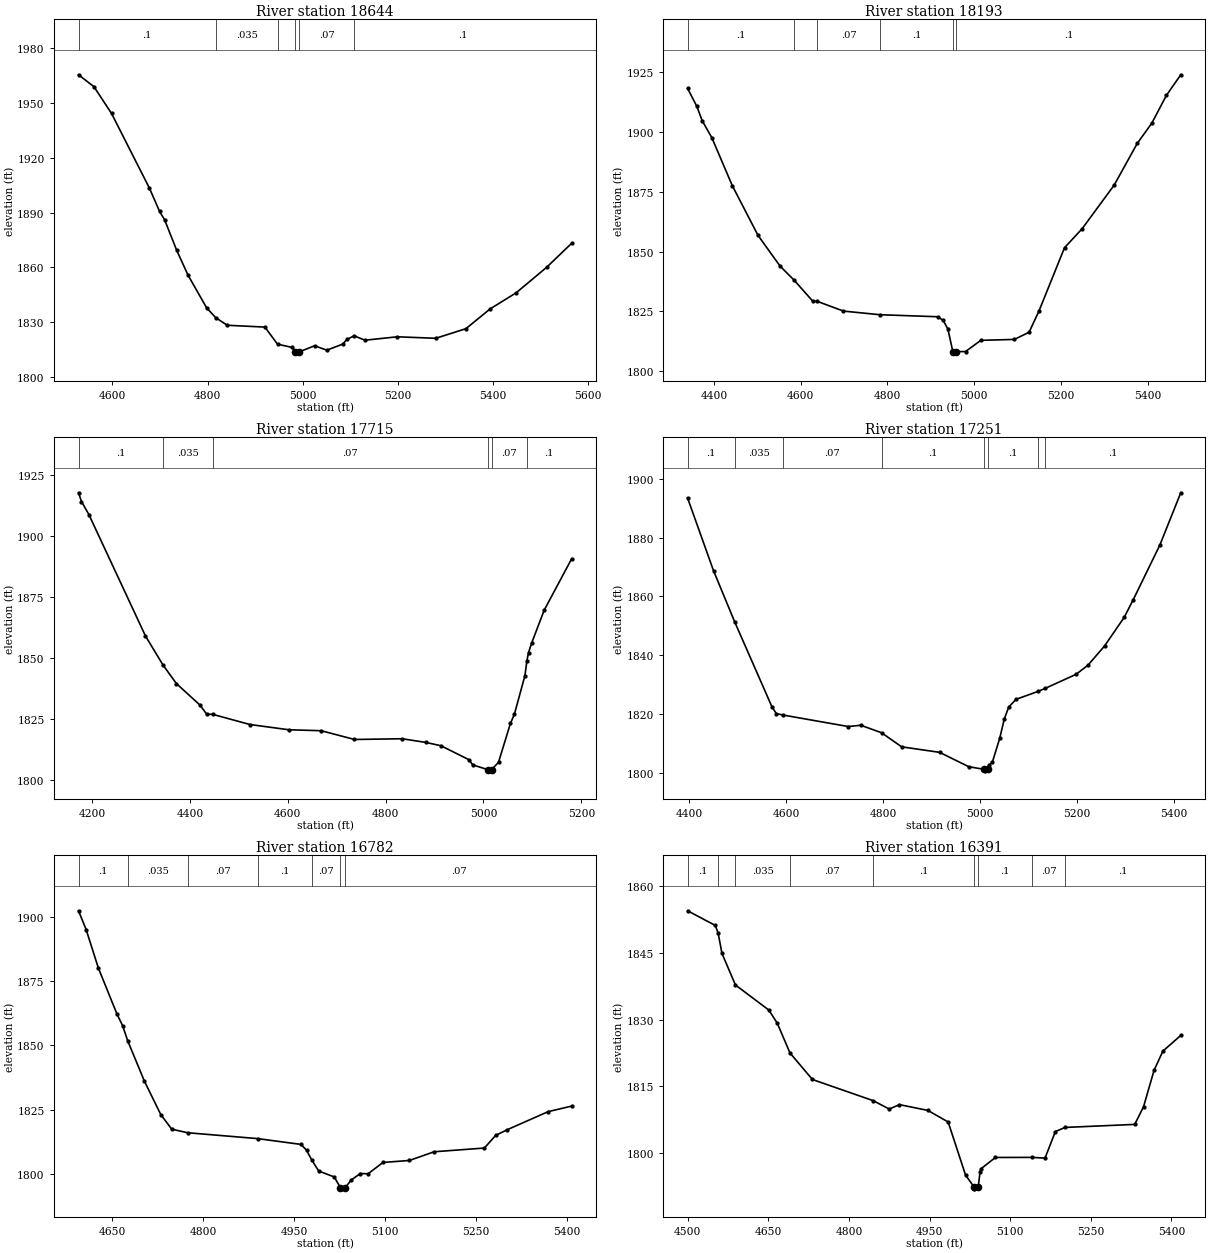
Type RM Length L Ch R = 1,18644,451,451,451
BEGIN DESCRIPTION:
East Town Creek 34.0
END DESCRIPTION:
XS GIS Cut Line= 3
      1928974.98     13954025.01      1928575.00     13954275.00
      1928174.97     13954675.03
#Sta/Elev= 30
  4528.6 1965.47  4561.1 1958.94  4598.1 1944.27  4677.9 1903.31  4699.1 1890.63
  4709.7 1886.05  4735.3 1869.22  4759.2 1855.61  4798.1 1837.81  4817.1 1832.45
  4841.5 1828.26  4920.7 1827.27  4947.2 1817.91  4978.6 1816.09  4984.7 1813.66
  4985.2 1813.16  4992.7 1813.66  5025.2 1817.03  5051.0 1814.62  5084.7 1817.98
  5093.2 1820.54  5108.4 1822.48  5131.2 1820.08  5199.3 1821.95  5280.1 1821.13
  5343.5 1826.39  5394.6 1837.24  5449.4 1846.07  5513.1 1859.96  5566.0 1873.17
#Mann=6,-1,0
  4528.6     0.1       0  4817.1   0.035       0  4947.2    0.07       0
  4984.7    0.05       0  4992.7    0.07       0  5108.4     0.1       0
Bank Sta=4984.7,4992.7
Exp/Cntr=0.3,0.1

Type RM Length L Ch R = 1,18193,478,478,478
BEGIN DESCRIPTION:
East Town Creek 33.0
END DESCRIPTION:
XS GIS Cut Line= 3
      1928712.54     13953731.86      1928175.00     13954125.00
      1927924.98     13954525.03
#Sta/Elev= 30
  4339.0 1918.31  4360.2 1910.83  4372.7 1904.78  4394.9 1897.69  4442.0 1877.65
  4501.5 1856.78  4552.4 1843.93  4585.4 1837.93  4627.8 1829.24  4638.3 1829.18
  4698.4 1825.12  4782.4 1823.60  4915.8 1822.75  4928.5 1821.24  4939.4 1817.65
  4950.9 1808.14  4951.4 1807.64  4958.9 1808.14  4980.2 1808.18  5015.4 1812.87
  5092.9 1813.26  5126.8 1816.26  5149.8 1825.23  5208.5 1851.64  5248.9 1859.53
  5323.2 1877.88  5376.2 1895.27  5409.9 1903.76  5443.5 1915.38  5476.7 1924.03
#Mann=6,-1,0
  4339.0     0.1       0  4585.4   0.035       0  4638.3    0.07       0
  4782.4     0.1       0  4950.9    0.05       0  4958.9     0.1       0
Bank Sta=4950.9,4958.9
Exp/Cntr=0.3,0.1

Type RM Length L Ch R = 1,17715,464,464,464
BEGIN DESCRIPTION:
East Town Creek 32.0
END DESCRIPTION:
XS GIS Cut Line= 3
      1928689.39     13953677.11      1927875.00     13953825.00
      1927724.99     13953925.01
#Sta/Elev= 30
  4172.2 1917.82  4178.3 1914.23  4193.5 1908.85  4309.1 1859.13  4345.3 1847.13
  4372.4 1839.63  4420.5 1830.82  4434.4 1827.06  4446.1 1827.06  4522.8 1822.86
  4602.1 1820.72  4668.3 1820.33  4736.3 1816.74  4833.8 1817.04  4882.6 1815.52
  4913.1 1814.16  4970.2 1808.46  4977.9 1806.34  5008.6 1804.39  5009.1 1803.89
  5016.7 1804.39  5030.7 1807.41  5055.0 1823.29  5063.1 1827.04  5084.7 1842.91
  5088.8 1849.09  5092.0 1852.34  5098.3 1856.16  5124.0 1869.70  5180.2 1890.78
#Mann=6,-1,0
  4172.2     0.1       0  4345.3   0.035       0  4446.1    0.07       0
  5008.6    0.05       0  5016.7    0.07       0  5088.8     0.1       0
Bank Sta=5008.6,5016.7
Exp/Cntr=0.3,0.1

Type RM Length L Ch R = 1,17251,469,469,469
BEGIN DESCRIPTION:
East Town Creek 31.0
END DESCRIPTION:
XS GIS Cut Line= 3
      1928526.85     13953413.60      1927918.38     13953376.82
      1927522.54     13953471.13
#Sta/Elev= 30
  4397.4 1893.40  4450.9 1868.68  4494.4 1851.34  4571.2 1822.46  4580.2 1820.16
  4593.0 1819.68  4728.2 1815.75  4754.5 1816.17  4797.1 1813.63  4838.6 1808.84
  4916.8 1806.97  4976.9 1802.08  5009.0 1801.18  5009.5 1800.68  5017.2 1801.18
  5019.3 1802.68  5025.5 1803.59  5040.9 1811.84  5050.2 1818.35  5059.4 1822.40
  5074.4 1824.99  5119.5 1827.67  5134.6 1828.72  5198.2 1833.50  5222.8 1836.62
  5256.8 1843.13  5297.1 1852.81  5315.3 1858.65  5370.9 1877.47  5413.9 1895.21
#Mann=8,-1,0
  4397.4     0.1       0  4494.4   0.035       0  4593.0    0.07       0
  4797.1     0.1       0  5009.0    0.05       0  5017.2     0.1       0
  5119.5    0.07       0  5134.6     0.1       0
Bank Sta=5009,5017.2
Exp/Cntr=0.3,0.1

Type RM Length L Ch R = 1,16782,391,391,391
BEGIN DESCRIPTION:
East Town Creek 30.0
END DESCRIPTION:
XS GIS Cut Line= 3
      1928524.98     13952975.00      1928125.00     13952975.00
      1927724.99     13953075.00
#Sta/Elev= 30
  4595.0 1902.31  4607.6 1894.97  4627.7 1880.05  4658.6 1862.02  4667.6 1857.67
  4676.1 1851.71  4703.6 1836.03  4730.6 1823.04  4748.6 1817.39  4774.7 1816.01
  4890.1 1813.73  4961.6 1811.47  4970.6 1809.20  4979.6 1805.24  4990.7 1801.12
  5016.2 1798.83  5026.3 1794.70  5026.8 1794.20  5034.5 1794.70  5044.0 1797.59
  5059.2 1800.16  5071.9 1800.05  5096.6 1804.46  5139.9 1805.23  5180.9 1808.62
  5263.6 1810.06  5282.1 1814.98  5300.7 1817.14  5368.7 1824.22  5407.3 1826.37
#Mann=7,-1,0
  4595.0     0.1       0  4676.1   0.035       0  4774.7    0.07       0
  4890.1     0.1       0  4979.6    0.07       0  5026.3    0.05       0
  5034.5    0.07       0
Bank Sta=5026.3,5034.5
Exp/Cntr=0.3,0.1

Type RM Length L Ch R = 1,16391,560,560,560
BEGIN DESCRIPTION:
East Town Creek 29.0
END DESCRIPTION:
XS GIS Cut Line= 3
      1928537.98     13952734.79      1928065.22     13952602.42
      1927675.02     13952774.99
#Sta/Elev= 30
  4499.9 1854.49  4551.4 1851.19  4556.7 1849.48  4563.8 1844.90  4588.9 1837.79
  4651.1 1832.14  4666.6 1829.22  4690.4 1822.49  4732.1 1816.52  4845.3 1811.75
  4875.1 1809.87  4894.1 1810.86  4947.0 1809.56  4984.7 1806.95  5017.1 1795.00
  5032.4 1792.41  5032.9 1791.91  5040.7 1792.41  5044.1 1795.75  5046.4 1796.48
  5072.6 1798.97  5141.3 1798.99  5164.9 1798.82  5184.2 1804.80  5202.1 1805.73
  5331.8 1806.41  5348.2 1810.37  5367.9 1818.61  5384.3 1822.91  5417.5 1826.43
#Mann=9,-1,0
  4499.9     0.1       0  4556.7    0.07       0  4588.9   0.035       0
  4690.4    0.07       0  4845.3     0.1       0  5032.4    0.05       0
  5040.7     0.1       0  5141.3    0.07       0  5202.1     0.1       0
Bank Sta=5032.4,5040.7
Exp/Cntr=0.3,0.1