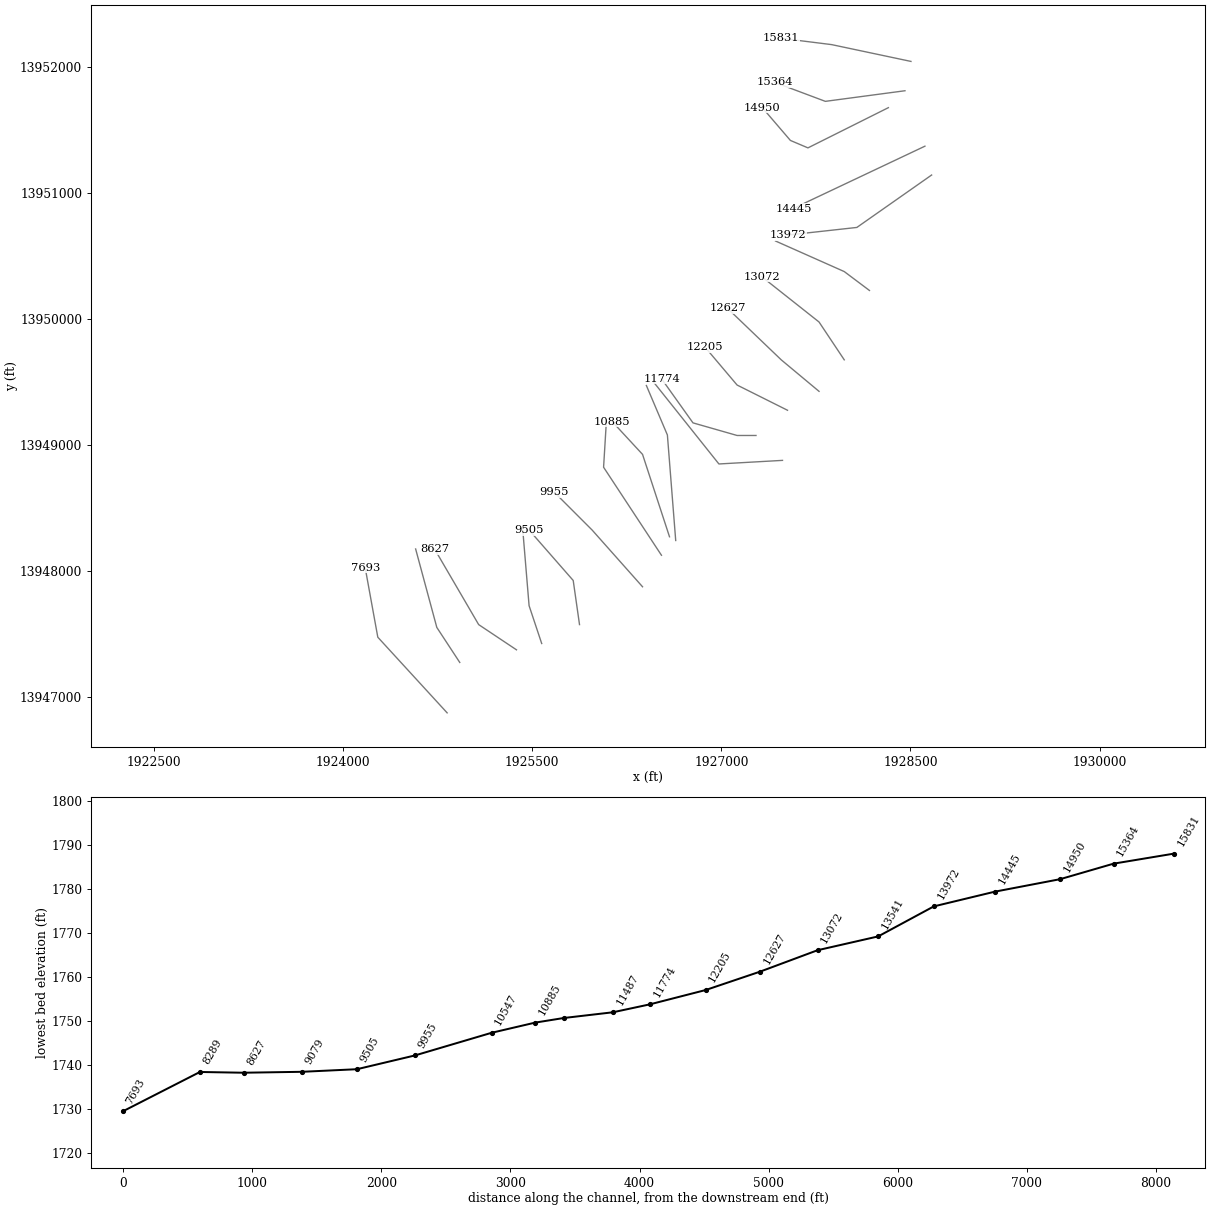
HEC-RAS study East Town Creek.prj: East Town Creek Base Level Engineering

--- East Town Creek.g01 (geometry) --- (continued)

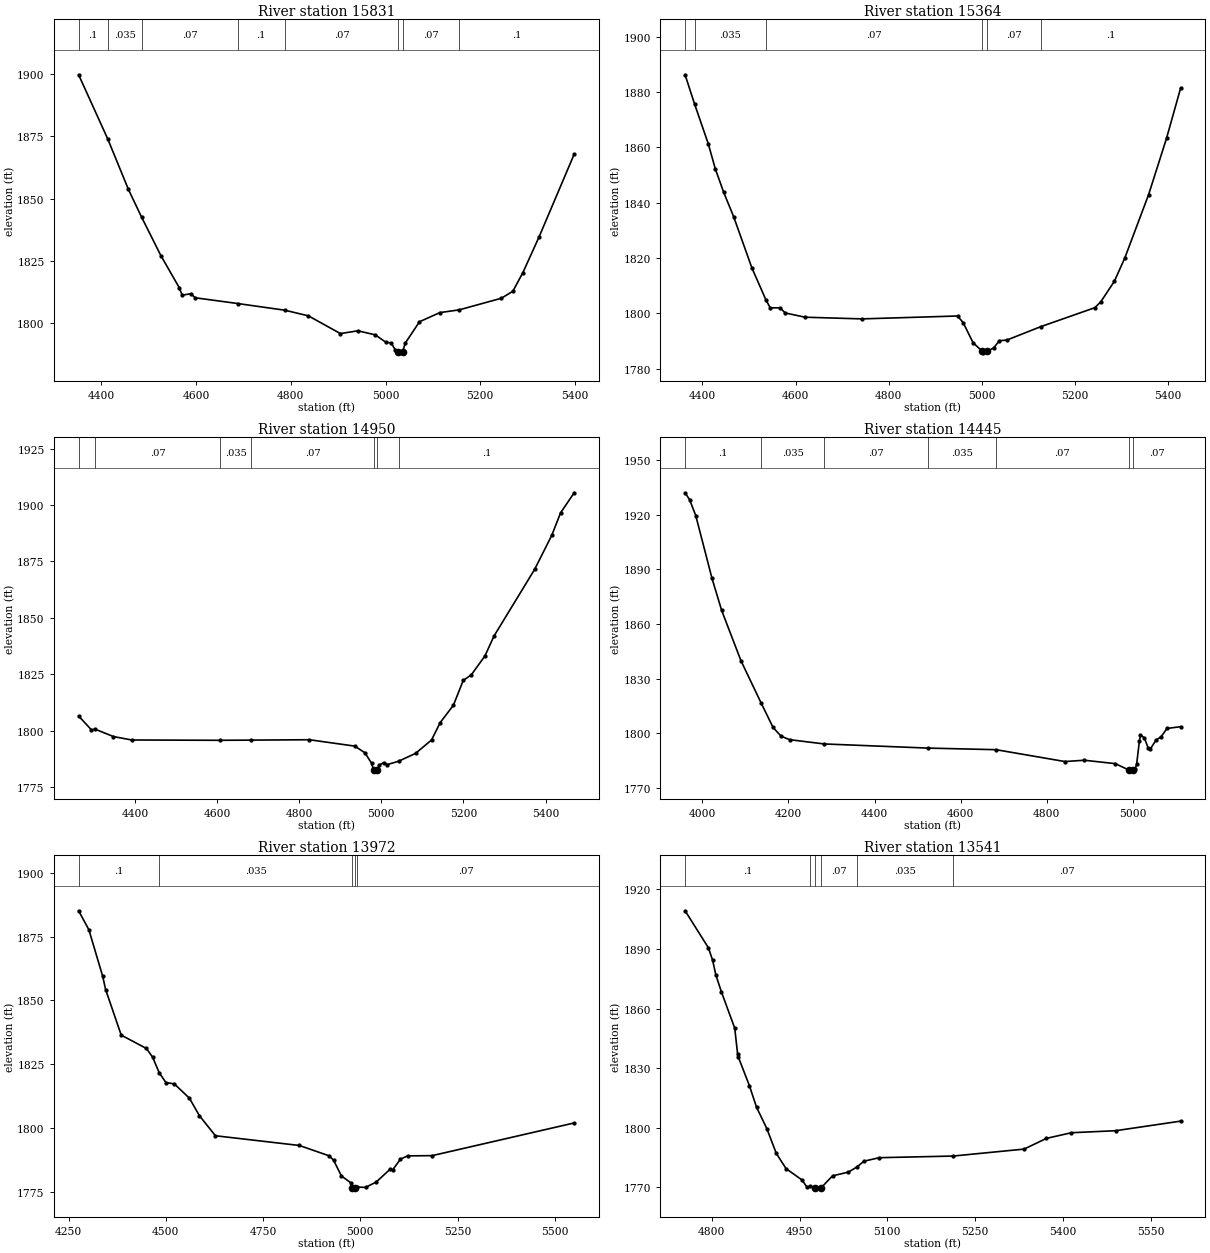
Type RM Length L Ch R = 1,15831,467,467,467
BEGIN DESCRIPTION:
East Town Creek 28.0
END DESCRIPTION:
XS GIS Cut Line= 3
      1928504.22     13952041.72      1927875.00     13952175.00
      1927475.00     13952225.00
#Sta/Elev= 30
  4351.9 1899.72  4413.6 1873.85  4457.0 1853.69  4484.9 1842.52  4525.6 1827.09
  4564.3 1814.25  4570.5 1811.22  4588.8 1811.80  4598.1 1810.17  4687.8 1807.86
  4787.3 1805.18  4836.9 1802.92  4904.7 1795.79  4941.5 1796.91  4978.3 1795.28
  5000.6 1792.31  5011.8 1792.05  5020.9 1789.08  5026.8 1788.56  5027.3 1788.06
  5035.8 1788.56  5042.0 1792.10  5071.6 1800.55  5114.6 1804.22  5155.2 1805.31
  5244.6 1809.99  5268.8 1812.81  5290.0 1820.31  5324.2 1834.67  5398.2 1867.82
#Mann=8,-1,0
  4351.9     0.1       0  4413.6   0.035       0  4484.9    0.07       0
  4687.8     0.1       0  4787.3    0.07       0  5026.8    0.05       0
  5035.8    0.07       0  5155.2     0.1       0
Bank Sta=5026.8,5035.8
Exp/Cntr=0.3,0.1

Type RM Length L Ch R = 1,15364,414,414,414
BEGIN DESCRIPTION:
East Town Creek 27.0
END DESCRIPTION:
XS GIS Cut Line= 3
      1928456.73     13951809.13      1927825.00     13951725.00
      1927425.00     13951875.00
#Sta/Elev= 30
  4362.7 1886.21  4383.3 1875.52  4412.5 1861.28  4427.6 1852.23  4445.7 1843.72
  4466.9 1834.99  4506.3 1816.40  4536.4 1804.88  4545.7 1802.02  4566.8 1802.04
  4577.8 1800.18  4620.5 1798.65  4742.3 1798.04  4948.1 1799.09  4960.2 1796.64
  4981.4 1789.41  5001.5 1786.28  5002.0 1785.78  5010.5 1786.28  5025.2 1787.53
  5038.0 1790.16  5054.0 1790.40  5126.3 1795.21  5243.1 1802.10  5255.9 1804.27
  5284.7 1811.60  5307.1 1819.97  5358.4 1842.93  5396.9 1863.27  5427.2 1881.42
#Mann=6,-1,0
  4362.7     0.1       0  4383.3   0.035       0  4536.4    0.07       0
  5001.5    0.05       0  5010.5    0.07       0  5126.3     0.1       0
Bank Sta=5001.5,5010.5
Exp/Cntr=0.3,0.1

Type RM Length L Ch R = 1,14950,505,505,505
BEGIN DESCRIPTION:
East Town Creek 26.0
END DESCRIPTION:
XS GIS Cut Line= 4
      1928324.96     13951674.98      1927686.98     13951355.99
      1927547.87     13951414.99      1927325.03     13951674.96
#Sta/Elev= 30
  4262.9 1806.53  4294.0 1800.43  4303.4 1800.68  4347.6 1797.44  4392.1 1795.92
  4606.9 1795.78  4683.6 1795.86  4824.8 1796.03  4935.5 1793.20  4960.3 1790.21
  4976.2 1785.63  4981.0 1782.75  4981.5 1782.25  4990.0 1782.75  4995.3 1784.81
  5005.5 1785.87  5014.8 1785.03  5041.9 1786.49  5083.4 1789.98  5122.4 1795.93
  5143.4 1803.61  5175.6 1811.31  5199.5 1822.28  5219.3 1824.81  5252.3 1833.12
  5274.6 1842.01  5373.4 1871.49  5415.3 1886.63  5436.6 1896.55  5469.7 1905.43
#Mann=7,-1,0
  4262.9   0.035       0  4303.4    0.07       0  4606.9   0.035       0
  4683.6    0.07       0  4981.0    0.05       0  4990.0    0.07       0
  5041.9     0.1       0
Bank Sta=4981,4990
Exp/Cntr=0.3,0.1

Type RM Length L Ch R = 1,14445,473,473,473
BEGIN DESCRIPTION:
East Town Creek 25.0
END DESCRIPTION:
XS GIS Cut Line= 3
      1928614.96     13951369.46      1927675.00     13950925.00
      1927575.04     13950875.02
#Sta/Elev= 30
  3959.8 1931.94  3970.4 1928.09  3984.6 1919.40  4022.3 1885.00  4044.8 1867.38
  4089.8 1839.70  4136.3 1816.71  4164.2 1803.22  4182.7 1798.44  4202.5 1796.51
  4283.2 1794.16  4524.1 1791.89  4682.4 1791.01  4842.4 1784.51  4887.4 1785.22
  4959.3 1783.36  4990.6 1779.91  4991.1 1779.41  4999.8 1779.91  5005.8 1780.55
  5009.0 1782.96  5015.5 1795.80  5018.0 1799.06  5026.9 1797.58  5036.0 1791.87
  5040.3 1791.15  5053.8 1796.20  5066.2 1798.20  5079.6 1802.67  5111.3 1803.62
#Mann=7,-1,0
  3959.8     0.1       0  4136.3   0.035       0  4283.2    0.07       0
  4524.1   0.035       0  4682.4    0.07       0  4990.6    0.05       0
  4999.8    0.07       0
Bank Sta=4990.6,4999.8
Exp/Cntr=0.3,0.1

Type RM Length L Ch R = 1,13972,431,431,431
BEGIN DESCRIPTION:
East Town Creek 24.0
END DESCRIPTION:
XS GIS Cut Line= 3
      1928668.10     13951140.82      1928075.00     13950725.00
      1927528.47     13950664.63
#Sta/Elev= 30
  4275.7 1885.11  4302.0 1877.69  4337.6 1859.40  4345.1 1854.22  4385.2 1836.35
  4449.9 1831.11  4465.8 1827.75  4483.0 1821.56  4500.2 1817.74  4521.7 1817.22
  4560.5 1811.63  4586.3 1804.74  4627.5 1796.88  4843.2 1793.07  4920.2 1788.99
  4931.2 1787.29  4951.5 1781.10  4975.1 1778.49  4978.0 1776.56  4978.5 1776.06
  4987.2 1776.56  4992.4 1776.74  5013.4 1776.63  5040.6 1778.70  5076.1 1783.67
  5083.1 1783.49  5103.1 1787.68  5121.4 1788.99  5184.7 1789.08  5549.9 1801.90
#Mann=5,-1,0
  4275.7     0.1       0  4483.0   0.035       0  4978.0    0.05       0
  4987.2   0.035       0  4992.4    0.07       0
Bank Sta=4978,4987.2
Exp/Cntr=0.3,0.1

Type RM Length L Ch R = 1,13541,469,469,469
BEGIN DESCRIPTION:
East Town Creek 23.0
END DESCRIPTION:
XS GIS Cut Line= 3
      1928175.02     13950224.98      1927975.00     13950375.00
      1927429.86     13950617.33
#Sta/Elev= 30
  4754.5 1909.26  4794.3 1890.64  4801.5 1884.37  4807.0 1877.00  4816.5 1868.43
  4839.3 1850.14  4844.3 1836.89  4845.6 1835.48  4864.3 1821.23  4876.5 1810.38
  4894.3 1799.45  4910.3 1787.08  4927.0 1779.41  4954.3 1773.68  4962.8 1770.02
  4968.6 1770.67  4976.3 1769.73  4976.8 1769.23  4986.8 1769.73  5006.4 1775.77
  5033.6 1777.67  5048.7 1780.36  5059.9 1783.13  5086.2 1784.92  5212.3 1785.74
  5333.6 1789.24  5371.8 1794.64  5414.5 1797.49  5490.0 1798.50  5601.1 1803.33
#Mann=6,-1,0
  4754.5     0.1       0  4968.6    0.07       0  4976.3    0.05       0
  4986.8    0.07       0  5048.7   0.035       0  5212.3    0.07       0
Bank Sta=4976.3,4986.8
Exp/Cntr=0.3,0.1

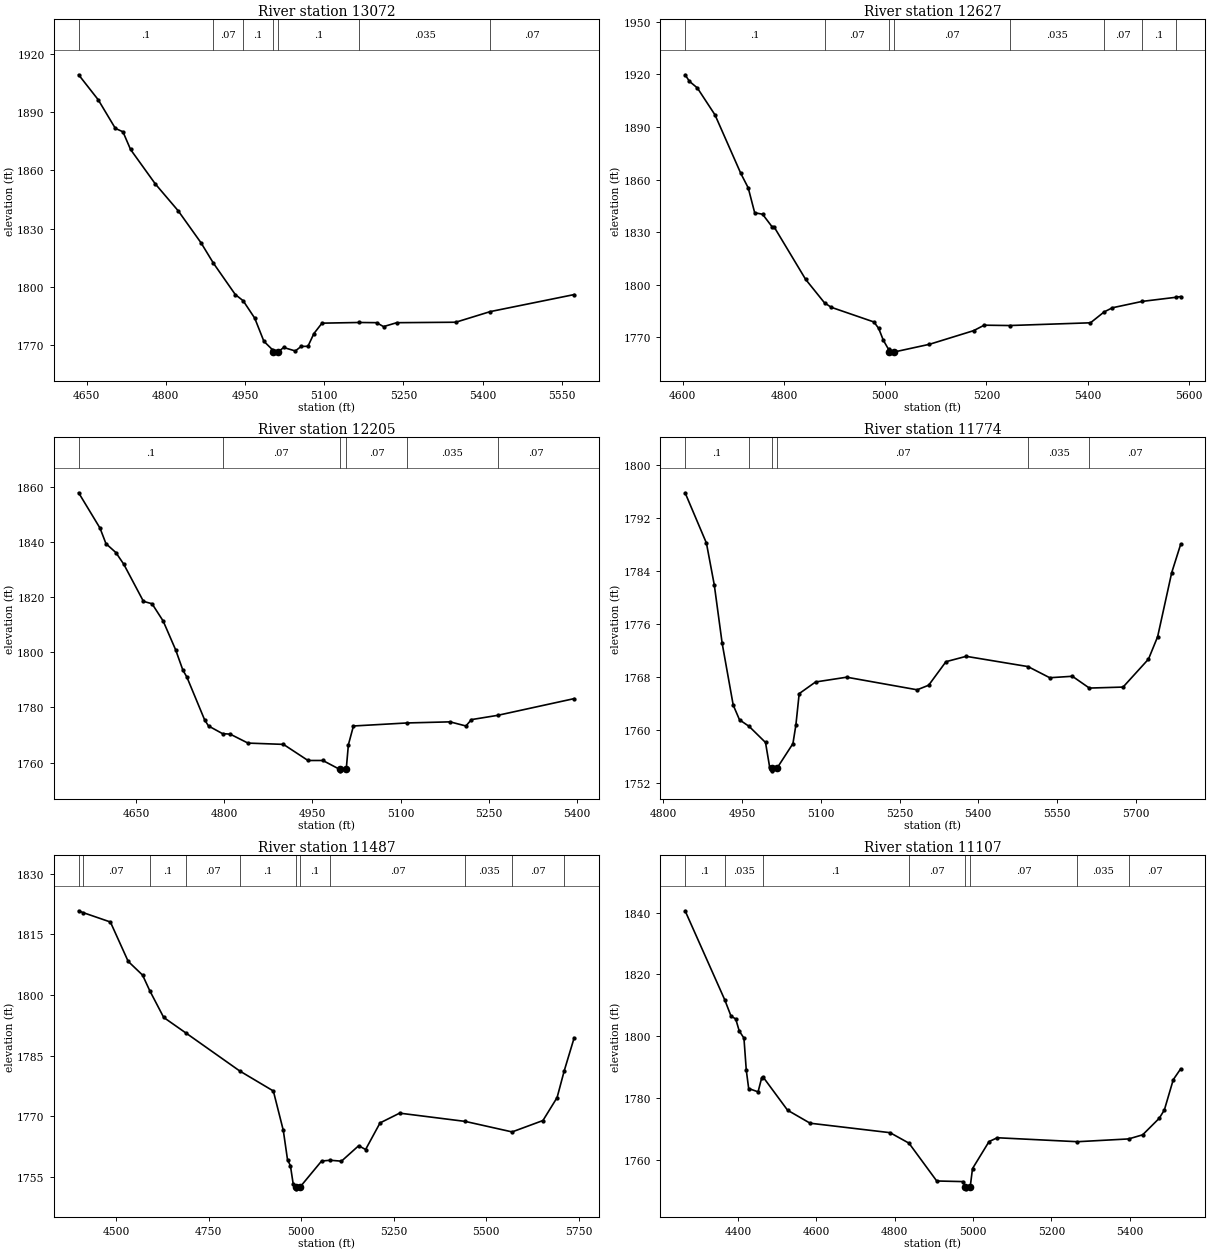
Type RM Length L Ch R = 1,13072,445,445,445
BEGIN DESCRIPTION:
East Town Creek 22.0
END DESCRIPTION:
XS GIS Cut Line= 3
      1927974.98     13949675.03      1927775.00     13949975.00
      1927321.98     13950333.30
#Sta/Elev= 30
  4635.1 1909.17  4672.1 1896.34  4704.6 1881.59  4719.0 1879.83  4733.4 1870.73
  4780.3 1853.00  4823.6 1839.17  4866.8 1822.71  4890.3 1812.21  4931.7 1796.07
  4946.5 1792.92  4968.5 1783.92  4985.8 1772.03  5001.8 1767.76  5002.5 1766.59
  5003.0 1766.09  5013.1 1766.59  5023.1 1768.85  5045.3 1767.06  5056.4 1769.40
  5069.2 1769.45  5080.5 1776.01  5095.8 1781.36  5165.7 1781.71  5199.1 1781.61
  5212.3 1779.59  5237.3 1781.60  5349.0 1781.84  5414.2 1787.30  5573.2 1796.07
#Mann=7,-1,0
  4635.1     0.1       0  4890.3    0.07       0  4946.5     0.1       0
  5002.5    0.05       0  5013.1     0.1       0  5165.7   0.035       0
  5414.2    0.07       0
Bank Sta=5002.5,5013.1
Exp/Cntr=0.3,0.1

Type RM Length L Ch R = 1,12627,422,422,422
BEGIN DESCRIPTION:
East Town Creek 21.0
END DESCRIPTION:
XS GIS Cut Line= 3
      1927775.01     13949424.99      1927475.00     13949675.00
      1927050.10     13950082.28
#Sta/Elev= 30
  4604.6 1919.77  4613.2 1916.03  4628.8 1912.26  4663.7 1896.89  4714.7 1863.51
  4729.3 1855.30  4742.1 1841.10  4757.7 1840.25  4776.2 1833.20  4781.1 1832.72
  4842.8 1803.09  4880.1 1789.72  4893.3 1787.20  4977.7 1778.82  4987.1 1775.15
  4996.3 1768.38  5006.7 1763.16  5007.2 1761.72  5007.7 1761.22  5017.9 1761.72
  5087.4 1766.09  5174.6 1773.86  5195.6 1776.99  5245.7 1776.79  5405.6 1778.35
  5432.7 1784.58  5448.9 1786.92  5507.9 1790.56  5573.6 1792.87  5583.7 1793.32
#Mann=8,-1,0
  4604.6     0.1       0  4880.1    0.07       0  5007.2    0.05       0
  5017.9    0.07       0  5245.7   0.035       0  5432.7    0.07       0
  5507.9     0.1       0  5573.6    0.07       0
Bank Sta=5007.2,5017.9
Exp/Cntr=0.3,0.1

Type RM Length L Ch R = 1,12205,431,431,431
BEGIN DESCRIPTION:
East Town Creek 20.0
END DESCRIPTION:
XS GIS Cut Line= 3
      1927525.00     13949275.00      1927125.00     13949475.00
      1926869.55     13949777.05
#Sta/Elev= 30
  4552.3 1857.83  4588.7 1845.00  4598.8 1839.38  4615.6 1836.17  4629.0 1831.96
  4662.5 1818.48  4677.2 1817.59  4696.1 1811.33  4717.4 1800.84  4729.6 1793.53
  4736.3 1791.07  4766.5 1775.55  4773.2 1773.29  4797.0 1770.52  4810.1 1770.33
  4840.3 1767.09  4900.7 1766.62  4942.4 1760.78  4967.7 1760.78  4996.6 1757.53
  4997.1 1757.03  5007.4 1757.53  5011.1 1766.49  5019.7 1773.29  5110.9 1774.39
  5184.0 1774.79  5211.0 1773.29  5220.3 1775.60  5265.0 1777.15  5395.1 1783.21
#Mann=6,-1,0
  4552.3     0.1       0  4797.0    0.07       0  4996.6    0.05       0
  5007.4    0.07       0  5110.9   0.035       0  5265.0    0.07       0
Bank Sta=4996.6,5007.4
Exp/Cntr=0.3,0.1

Type RM Length L Ch R = 1,11774,287,287,287
BEGIN DESCRIPTION:
East Town Creek 19.0
END DESCRIPTION:
XS GIS Cut Line= 4
      1927274.99     13949075.00      1927125.00     13949075.00
      1926775.00     13949175.00      1926525.81     13949524.70
#Sta/Elev= 30
  4841.8 1795.74  4882.4 1788.15  4897.4 1781.82  4912.4 1773.01  4933.4 1763.70
  4945.4 1761.48  4963.8 1760.48  4994.9 1758.06  5002.8 1754.33  5006.8 1754.28
  5007.3 1753.78  5017.6 1754.28  5047.1 1757.89  5052.7 1760.68  5059.0 1765.43
  5090.2 1767.19  5149.4 1767.91  5283.6 1766.01  5305.5 1766.70  5338.4 1770.25
  5376.9 1771.06  5494.7 1769.51  5536.0 1767.83  5579.1 1768.05  5611.4 1766.27
  5675.6 1766.42  5724.0 1770.64  5741.4 1774.02  5768.2 1783.69  5785.2 1787.95
#Mann=6,-1,0
  4841.8     0.1       0  4963.8    0.07       0  5006.8    0.05       0
  5017.6    0.07       0  5494.7   0.035       0  5611.4    0.07       0
Bank Sta=5006.8,5017.6
Exp/Cntr=0.3,0.1

Type RM Length L Ch R = 1,11487,380,380,380
BEGIN DESCRIPTION:
East Town Creek 18.0
END DESCRIPTION:
XS GIS Cut Line= 3
      1927485.17     13948877.51      1926980.72     13948849.04
      1926459.94     13949501.93
#Sta/Elev= 30
  4397.8 1820.85  4409.8 1820.40  4483.7 1818.07  4531.8 1808.32  4570.8 1804.91
  4590.1 1801.07  4627.9 1794.43  4688.7 1790.53  4833.8 1781.15  4924.5 1776.21
  4951.4 1766.45  4962.9 1759.14  4970.6 1757.73  4978.3 1753.10  4986.4 1752.47
  4986.9 1751.97  4997.2 1752.47  5055.0 1758.86  5078.5 1759.05  5108.7 1758.82
  5155.3 1762.65  5174.0 1761.71  5213.1 1768.30  5266.1 1770.72  5443.8 1768.67
  5570.3 1766.07  5653.7 1768.89  5692.0 1774.58  5711.4 1781.24  5738.2 1789.39
#Mann=11,-1,0
  4397.8   0.035       0  4409.8    0.07       0  4590.1     0.1       0
  4688.7    0.07       0  4833.8     0.1       0  4986.4    0.05       0
  4997.2     0.1       0  5078.5    0.07       0  5443.8   0.035       0
  5570.3    0.07       0  5711.4     0.1       0
Bank Sta=4986.4,4997.2
Exp/Cntr=0.3,0.1

Type RM Length L Ch R = 1,11107,222,222,222
BEGIN DESCRIPTION:
East Town Creek 17.1
END DESCRIPTION:
XS GIS Cut Line= 3
      1926638.07     13948241.98      1926572.09     13949078.82
      1926405.43     13949471.15
#Sta/Elev= 30
  4264.6 1840.58  4365.9 1811.78  4381.8 1806.55  4393.9 1805.59  4402.9 1801.71
  4414.9 1799.41  4420.9 1789.00  4427.0 1783.11  4451.0 1782.03  4460.1 1786.50
  4464.3 1786.74  4526.3 1776.10  4583.9 1771.89  4788.1 1768.83  4836.4 1765.44
  4907.3 1753.21  4974.7 1753.01  4980.6 1751.17  4981.1 1750.67  4992.7 1751.17
  4998.7 1757.22  5040.9 1765.95  5061.9 1767.19  5266.8 1765.91  5397.5 1766.81
  5433.3 1768.14  5475.6 1773.48  5488.7 1776.17  5511.5 1785.98  5530.3 1789.46
#Mann=8,-1,0
  4264.6     0.1       0  4365.9   0.035       0  4464.3     0.1       0
  4836.4    0.07       0  4980.6    0.05       0  4992.7    0.07       0
  5266.8   0.035       0  5397.5    0.07       0
Bank Sta=4980.6,4992.7
Exp/Cntr=0.3,0.1

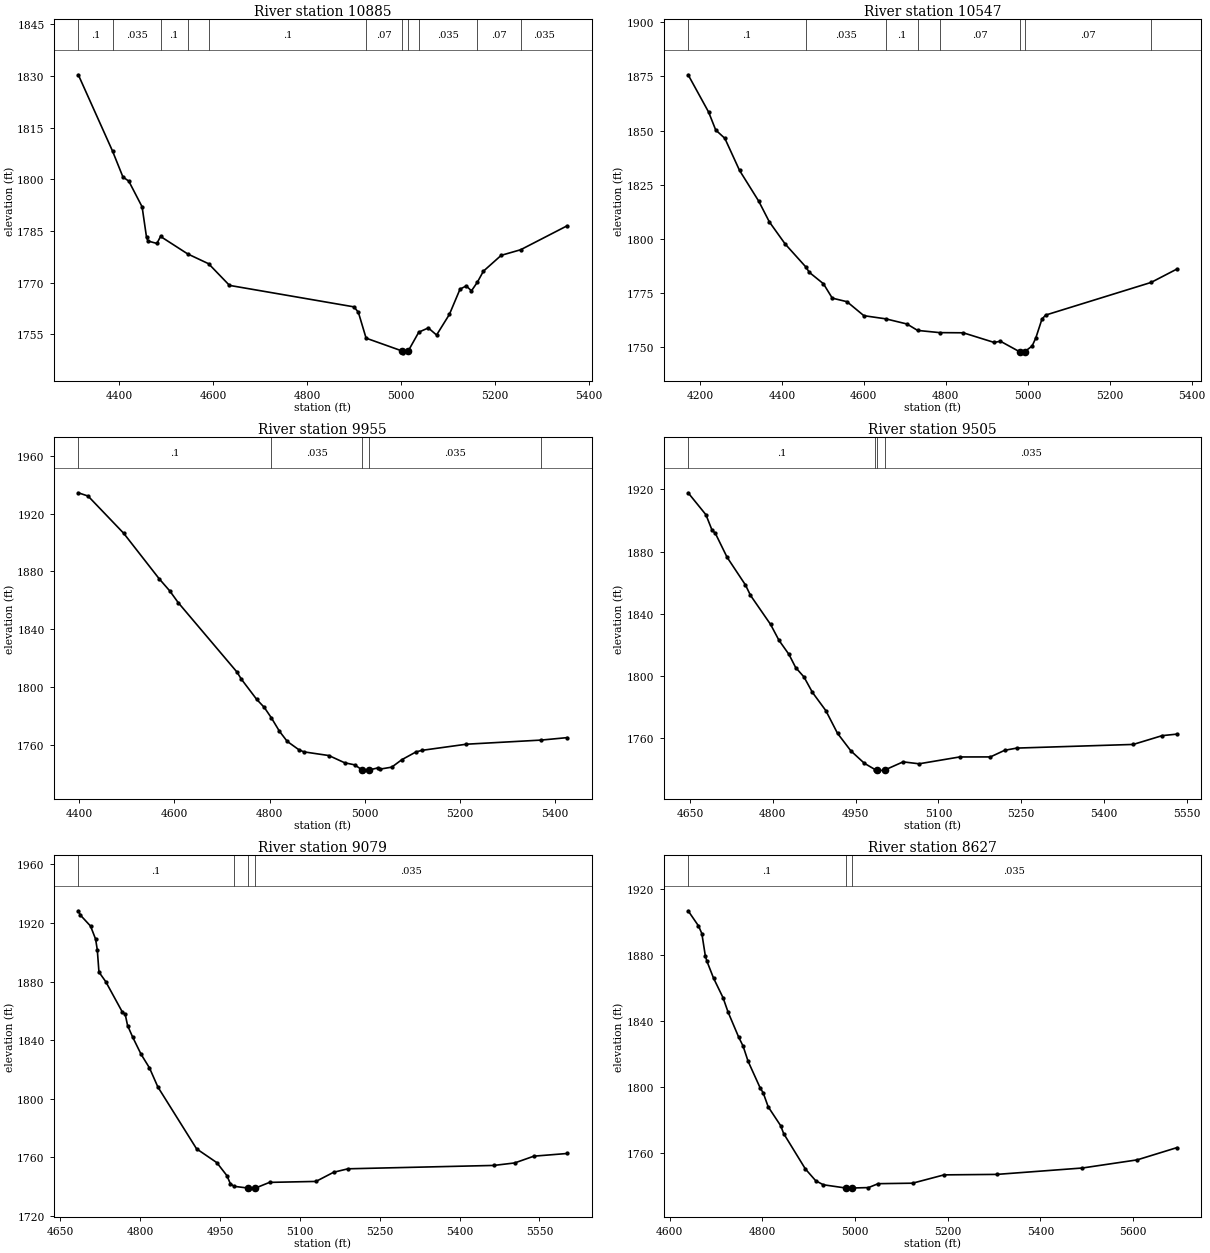
Type RM Length L Ch R = 1,10885,338,338,338
BEGIN DESCRIPTION:
East Town Creek 17.0
END DESCRIPTION:
XS GIS Cut Line= 3
      1926588.85     13948271.61      1926375.00     13948925.00
      1926134.42     13949184.96
#Sta/Elev= 30
  4312.5 1830.30  4385.4 1808.18  4407.6 1800.65  4420.1 1799.44  4448.5 1791.98
  4457.9 1783.14  4461.1 1782.06  4480.0 1781.36  4487.8 1783.39  4545.6 1778.32
  4590.2 1775.47  4634.7 1769.19  4899.9 1762.96  4909.3 1761.40  4925.8 1753.88
  5003.3 1750.12  5003.8 1749.62  5015.4 1750.12  5038.1 1755.62  5058.4 1756.85
  5076.0 1754.79  5103.3 1760.77  5126.0 1768.11  5139.3 1769.04  5150.3 1767.60
  5162.9 1770.11  5175.8 1773.31  5213.7 1777.91  5255.1 1779.53  5354.2 1786.48
#Mann=11,-1,0
  4312.5     0.1       0  4385.4   0.035       0  4487.8     0.1       0
  4545.6   0.035       0  4590.2     0.1       0  4925.8    0.07       0
  5003.3    0.05       0  5015.4    0.07       0  5038.1   0.035       0
  5162.9    0.07       0  5255.1   0.035       0
Bank Sta=5003.3,5015.4
Exp/Cntr=0.3,0.1

Type RM Length L Ch R = 1,10547,592,592,592
BEGIN DESCRIPTION:
East Town Creek 16.0
END DESCRIPTION:
XS GIS Cut Line= 3
      1926525.01     13948124.98      1926065.94     13948823.11
      1926087.61     13949179.60
#Sta/Elev= 30
  4171.3 1875.79  4221.4 1858.51  4238.6 1850.27  4260.9 1846.42  4296.8 1831.58
  4343.5 1817.41  4369.5 1807.81  4408.1 1797.59  4458.7 1786.94  4466.9 1784.51
  4501.5 1779.21  4523.0 1772.58  4558.9 1770.93  4600.1 1764.47  4653.5 1763.01
  4705.2 1760.63  4731.2 1757.66  4785.2 1756.64  4842.6 1756.56  4918.0 1752.10
  4933.2 1752.67  4980.1 1747.80  4980.6 1747.30  4992.2 1747.80  5010.6 1750.45
  5019.6 1754.16  5034.6 1762.88  5043.6 1764.75  5301.0 1779.84  5364.0 1786.03
#Mann=8,-1,0
  4171.3     0.1       0  4458.7   0.035       0  4653.5     0.1       0
  4731.2   0.035       0  4785.2    0.07       0  4980.1    0.05       0
  4992.2    0.07       0  5301.0   0.035       0
Bank Sta=4980.1,4992.2
Exp/Cntr=0.3,0.1

Type RM Length L Ch R = 1,9955,450,450,450
BEGIN DESCRIPTION:
East Town Creek 15.0
END DESCRIPTION:
XS GIS Cut Line= 3
      1926375.00     13947875.00      1925975.00     13948325.00
      1925675.03     13948624.97
#Sta/Elev= 30
  4398.5 1934.32  4419.0 1932.05  4493.7 1906.37  4568.2 1874.94  4590.6 1866.48
  4608.3 1858.40  4731.7 1810.41  4740.8 1805.54  4772.9 1791.61  4789.0 1785.99
  4803.8 1778.82  4820.8 1769.53  4837.1 1762.53  4861.5 1756.77  4872.0 1755.28
  4924.7 1752.72  4957.6 1747.75  4978.9 1746.28  4994.9 1742.66  4995.4 1742.16
  5007.9 1742.66  5026.9 1744.15  5031.1 1743.30  5056.6 1744.71  5077.8 1749.87
  5107.5 1755.23  5120.4 1756.34  5213.5 1760.57  5370.6 1763.42  5424.8 1765.11
#Mann=5,-1,0
  4398.5     0.1       0  4803.8   0.035       0  4994.9   0.035       0
  5007.9   0.035       0  5370.6    0.07       0
Bank Sta=4994.9,5007.9
Exp/Cntr=0.3,0.1

Type RM Length L Ch R = 1,9505,426,426,426
BEGIN DESCRIPTION:
East Town Creek 14.0
END DESCRIPTION:
XS GIS Cut Line= 3
      1925874.99     13947575.05      1925825.00     13947925.00
      1925475.01     13948324.99
#Sta/Elev= 30
  4646.8 1917.80  4679.0 1903.70  4690.0 1893.86  4696.1 1891.72  4717.3 1876.37
  4750.6 1858.52  4759.7 1851.86  4796.1 1833.15  4811.2 1823.00  4829.4 1813.86
  4841.5 1805.43  4856.6 1799.35  4871.9 1789.43  4896.1 1777.75  4917.3 1763.12
  4941.6 1751.81  4965.8 1743.89  4985.5 1739.79  4989.6 1739.52  4990.1 1739.02
  5002.6 1739.52  5036.0 1744.79  5065.0 1743.55  5138.3 1747.94  5194.1 1747.97
  5219.9 1752.23  5241.9 1753.65  5452.7 1756.00  5505.0 1761.65  5531.8 1762.63
#Mann=4,-1,0
  4646.8     0.1       0  4985.5   0.035       0  4989.6   0.035       0
  5002.6   0.035       0
Bank Sta=4989.6,5002.6
Exp/Cntr=0.3,0.1

Type RM Length L Ch R = 1,9079,452,452,452
BEGIN DESCRIPTION:
East Town Creek 13.0
END DESCRIPTION:
XS GIS Cut Line= 3
      1925575.00     13947425.01      1925475.00     13947725.00
      1925425.00     13948325.00
#Sta/Elev= 30
  4683.8 1928.35  4687.8 1925.36  4706.8 1917.90  4716.3 1909.01  4719.5 1901.66
  4722.6 1886.49  4735.3 1879.98  4766.4 1859.28  4771.9 1857.65  4776.4 1849.96
  4785.9 1842.11  4801.7 1830.38  4817.5 1821.04  4833.3 1807.99  4906.0 1765.76
  4944.0 1756.34  4963.0 1747.44  4969.3 1742.06  4976.0 1740.17  5003.4 1738.93
  5003.9 1738.43  5016.4 1738.93  5043.0 1742.84  5130.3 1743.49  5163.4 1749.75
  5190.5 1752.12  5464.5 1754.42  5503.6 1756.12  5539.7 1760.75  5602.1 1762.57
#Mann=4,-1,0
  4683.8     0.1       0  4976.0   0.035       0  5003.4   0.035       0
  5016.4   0.035       0
Bank Sta=5003.4,5016.4
Exp/Cntr=0.3,0.1

Type RM Length L Ch R = 1,8627,338,338,338
BEGIN DESCRIPTION:
East Town Creek 12.0
END DESCRIPTION:
XS GIS Cut Line= 3
      1925375.00     13947375.00      1925075.00     13947575.00
      1924724.99     13948175.02
#Sta/Elev= 30
  4639.6 1906.83  4661.9 1897.70  4669.2 1893.05  4676.7 1879.58  4680.0 1876.37
  4694.4 1866.04  4715.0 1854.10  4725.8 1845.43  4748.5 1830.35  4758.3 1824.74
  4769.1 1815.55  4795.3 1799.30  4801.6 1796.48  4812.4 1787.98  4839.4 1776.50
  4845.8 1771.75  4892.7 1750.28  4915.1 1743.11  4931.4 1740.69  4979.9 1738.72
  4980.4 1738.22  4993.0 1738.72  5028.9 1738.98  5049.8 1741.35  5124.0 1741.64
  5192.1 1746.69  5306.1 1746.98  5490.8 1750.86  5608.9 1755.78  5694.8 1763.21
#Mann=3,-1,0
  4639.6     0.1       0  4979.9   0.035       0  4993.0   0.035       0
Bank Sta=4979.9,4993
Exp/Cntr=0.3,0.1

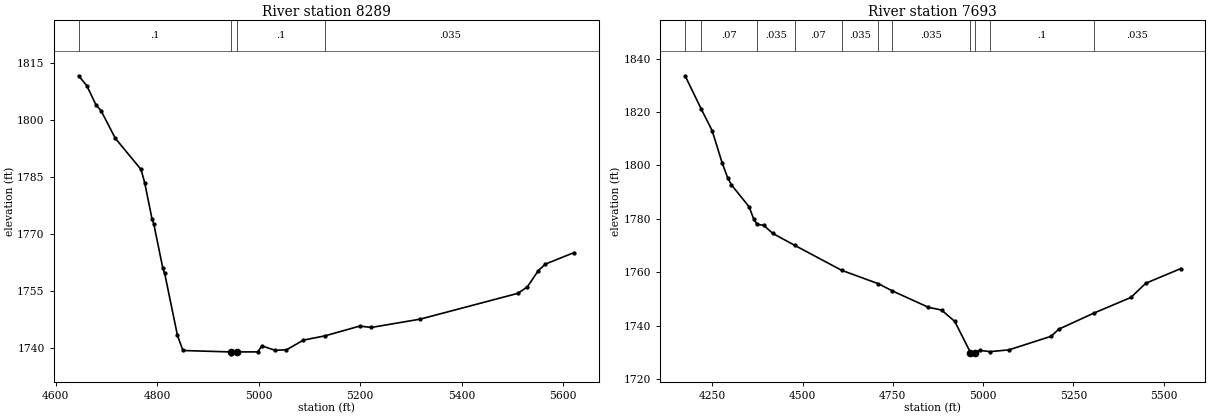
Type RM Length L Ch R = 1,8289,596,596,596
BEGIN DESCRIPTION:
East Town Creek 11.0
END DESCRIPTION:
XS GIS Cut Line= 3
      1924925.01     13947274.99      1924743.04     13947552.55
      1924575.01     13948174.98
#Sta/Elev= 30
  4645.2 1811.66  4661.4 1809.04  4679.1 1804.06  4689.3 1802.48  4717.4 1795.20
  4768.2 1786.97  4775.4 1783.47  4789.7 1774.03  4793.3 1772.63  4811.2 1760.91
  4814.8 1759.58  4839.9 1743.29  4850.7 1739.27  4944.6 1738.89  4945.1 1738.39
  4957.7 1738.89  4998.1 1738.91  5006.4 1740.48  5032.3 1739.32  5054.7 1739.44
  5088.2 1742.01  5130.7 1743.13  5199.4 1745.71  5221.8 1745.34  5318.2 1747.53
  5510.8 1754.33  5529.5 1756.03  5551.2 1760.33  5565.1 1762.04  5621.8 1765.08
#Mann=4,-1,0
  4645.2     0.1       0  4944.6    0.05       0  4957.7     0.1       0
  5130.7   0.035       0
Bank Sta=4944.6,4957.7
Exp/Cntr=0.3,0.1

Type RM Length L Ch R = 1,7693,486,486,486
BEGIN DESCRIPTION:
East Town Creek 10.0
END DESCRIPTION:
XS GIS Cut Line= 3
      1924824.99     13946875.01      1924275.00     13947475.00
      1924175.01     13948024.96
#Sta/Elev= 30
  4174.4 1833.54  4218.9 1821.15  4249.3 1813.02  4277.3 1800.84  4292.2 1795.44
  4302.5 1792.76  4351.9 1784.46  4364.7 1779.82  4374.2 1777.88  4392.0 1777.60
  4417.0 1774.55  4478.2 1770.06  4607.8 1760.74  4710.0 1755.69  4748.5 1753.01
  4848.4 1746.88  4885.0 1745.84  4921.6 1741.57  4965.0 1729.95  4965.5 1729.45
  4978.2 1729.95  4990.2 1730.76  5019.4 1730.28  5071.3 1730.93  5188.4 1736.02
  5209.7 1738.68  5305.9 1744.64  5409.8 1750.58  5450.6 1755.87  5547.3 1761.34
#Mann=11,-1,0
  4174.4     0.1       0  4218.9    0.07       0  4374.2   0.035       0
  4478.2    0.07       0  4607.8   0.035       0  4710.0    0.07       0
  4748.5   0.035       0  4965.0   0.035       0  4978.2   0.035       0
  5019.4     0.1       0  5305.9   0.035       0
Bank Sta=4965,4978.2
Exp/Cntr=0.3,0.1