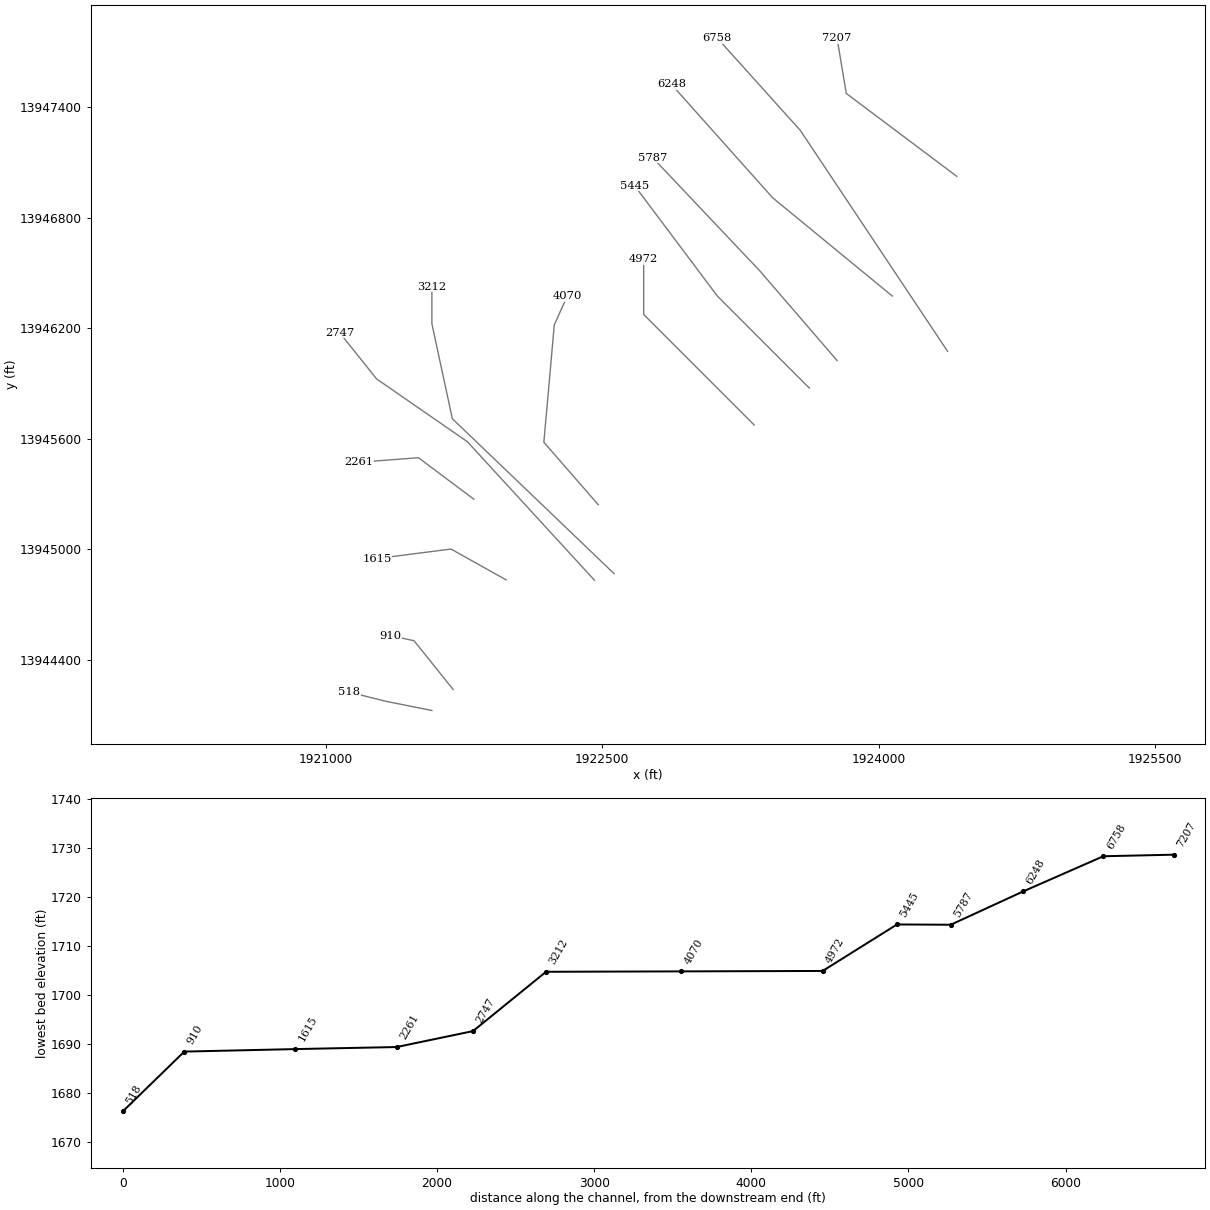
HEC-RAS study East Town Creek.prj: East Town Creek Base Level Engineering

--- East Town Creek.g01 (geometry) --- (continued)

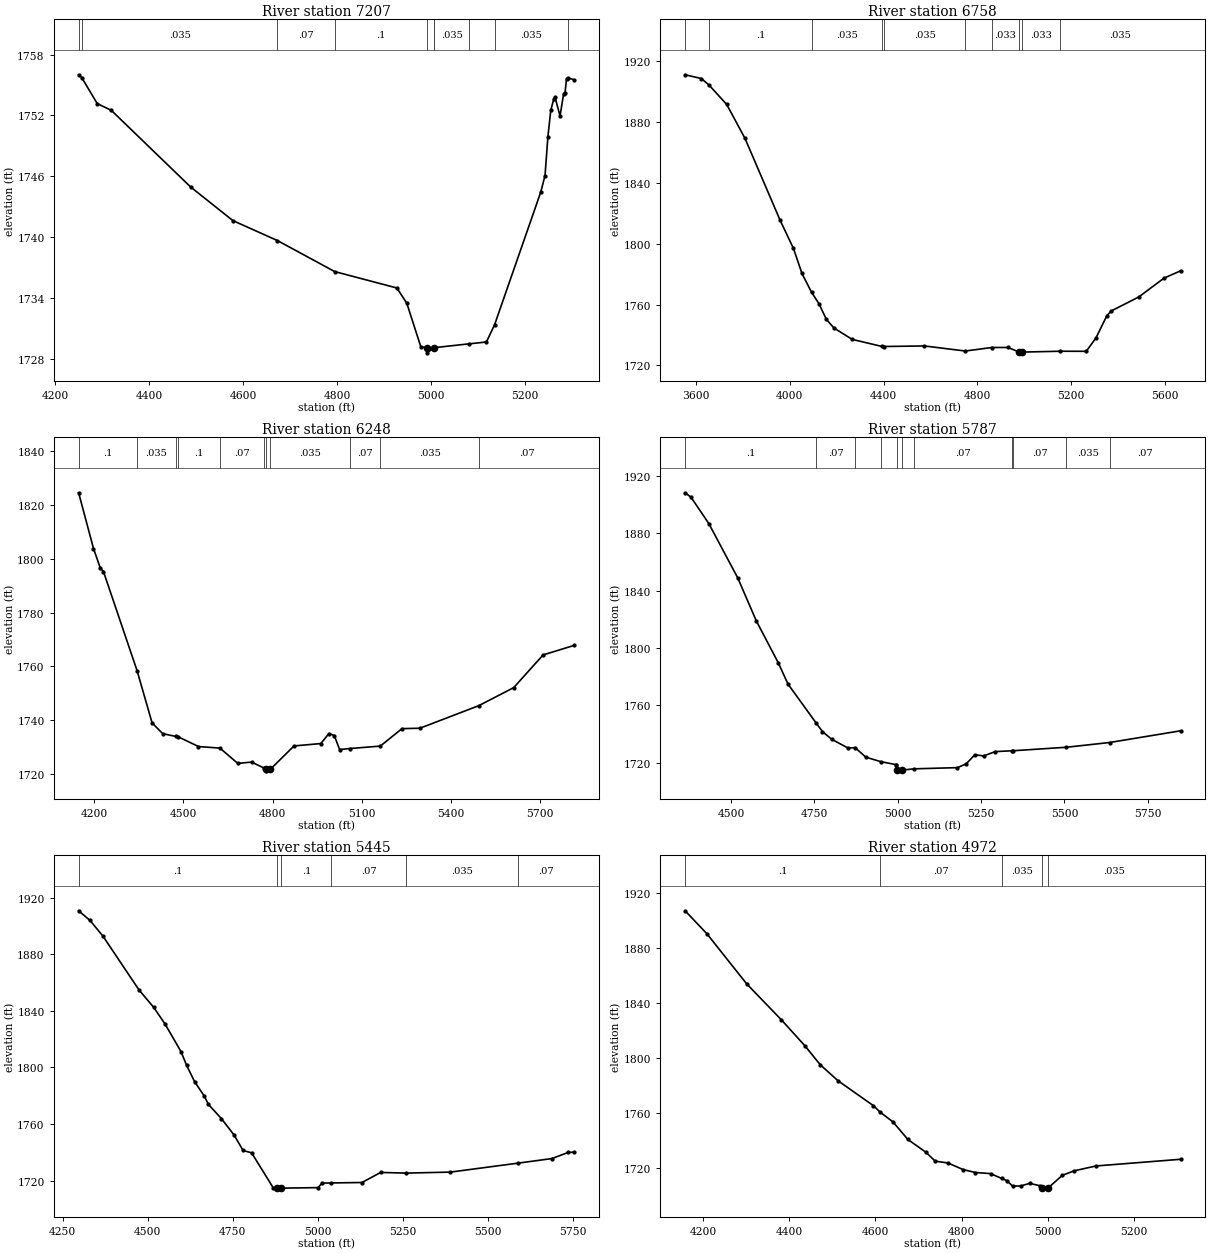
Type RM Length L Ch R = 1,7207,449,449,449
BEGIN DESCRIPTION:
East Town Creek 9.0
END DESCRIPTION:
XS GIS Cut Line= 3
      1924425.00     13947025.00      1923825.00     13947475.00
      1923775.01     13947774.97
#Sta/Elev= 30
  4250.0 1756.01  4256.5 1755.74  4289.5 1753.17  4319.5 1752.50  4488.2 1744.94
  4578.1 1741.62  4672.9 1739.65  4794.6 1736.59  4927.0 1734.97  4948.1 1733.46
  4978.1 1729.14  4991.6 1729.07  4992.1 1728.57  5004.9 1729.07  5006.2 1729.08
  5080.9 1729.46  5117.4 1729.64  5134.7 1731.33  5233.0 1744.43  5242.1 1746.07
  5248.2 1749.89  5254.3 1752.49  5260.4 1753.58  5263.4 1753.80  5274.0 1751.94
  5281.7 1754.13  5284.7 1754.25  5287.8 1755.61  5290.7 1755.70  5304.1 1755.52
#Mann=10,-1,0
  4250.0    0.07       0  4256.5   0.035       0  4672.9    0.07       0
  4794.6     0.1       0  4991.6    0.05       0  5004.9     0.1       0
  5006.2   0.035       0  5080.9     0.1       0  5134.7   0.035       0
  5290.7     0.1       0
Bank Sta=4991.6,5004.9
Exp/Cntr=0.3,0.1

Type RM Length L Ch R = 1,6758,510,510,510
BEGIN DESCRIPTION:
East Town Creek 8.0
END DESCRIPTION:
XS GIS Cut Line= 3
      1924375.02     13946074.97      1923575.00     13947275.00
      1923125.03     13947774.97
#Sta/Elev= 30
  3553.2 1911.17  3622.8 1908.69  3656.2 1904.27  3730.9 1891.63  3808.8 1869.34
  3958.1 1815.68  4015.8 1796.89  4051.8 1780.52  4092.8 1768.13  4124.7 1760.52
  4156.4 1750.20  4188.8 1744.56  4266.4 1737.10  4393.1 1732.46  4402.0 1732.42
  4574.6 1732.78  4749.2 1729.45  4862.1 1731.76  4931.6 1731.78  4979.0 1728.75
  4979.5 1728.25  4992.4 1728.75  5154.5 1729.31  5265.4 1729.26  5307.4 1738.25
  5353.3 1752.72  5373.0 1755.87  5489.6 1765.03  5597.3 1777.41  5668.1 1782.20
#Mann=10,-1,0
  3553.2    0.07       0  3656.2     0.1       0  4092.8   0.035       0
  4393.1    0.07       0  4402.0   0.035       0  4749.2     0.1       0
  4862.1   0.033       0  4979.0   0.033       0  4992.4   0.033       0
  5154.5   0.035       0
Bank Sta=4979,4992.4
Exp/Cntr=0.3,0.1

Type RM Length L Ch R = 1,6248,461,461,461
BEGIN DESCRIPTION:
East Town Creek 7.0
END DESCRIPTION:
XS GIS Cut Line= 3
      1924075.03     13946374.98      1923424.88     13946908.85
      1922875.00     13947525.00
#Sta/Elev= 30
  4147.3 1824.56  4197.3 1803.82  4220.6 1796.45  4230.8 1795.26  4344.0 1758.32
  4394.5 1738.90  4430.2 1734.92  4473.4 1733.89  4481.8 1733.76  4550.5 1730.12
  4622.6 1729.53  4682.8 1723.84  4729.1 1724.33  4771.8 1722.07  4778.3 1721.57
  4778.8 1721.07  4791.7 1721.57  4871.9 1730.34  4961.9 1731.22  4989.6 1734.96
  5007.3 1734.22  5025.3 1729.00  5058.7 1729.36  5162.4 1730.29  5235.2 1736.78
  5295.6 1736.93  5493.7 1745.34  5611.0 1752.04  5709.9 1764.21  5814.4 1767.76
#Mann=11,-1,0
  4147.3     0.1       0  4344.0   0.035       0  4473.4    0.07       0
  4481.8     0.1       0  4622.6    0.07       0  4771.8   0.035       0
  4778.3   0.035       0  4791.7   0.035       0  5058.7    0.07       0
  5162.4   0.035       0  5493.7    0.07       0
Bank Sta=4778.3,4791.7
Exp/Cntr=0.3,0.1

Type RM Length L Ch R = 1,5787,342,342,342
BEGIN DESCRIPTION:
East Town Creek 6.0
END DESCRIPTION:
XS GIS Cut Line= 3
      1923775.00     13946025.00      1923356.60     13946510.56
      1922775.00     13947125.00
#Sta/Elev= 30
  4361.8 1908.23  4379.6 1905.10  4432.9 1886.79  4520.0 1848.75  4575.4 1818.91
  4641.5 1789.60  4670.5 1774.83  4755.1 1747.59  4774.1 1741.63  4801.2 1736.36
  4850.6 1730.19  4872.1 1730.43  4904.1 1723.80  4949.0 1720.68  4993.2 1718.67
  4995.4 1718.16  4997.7 1714.77  4998.2 1714.27  5011.2 1714.77  5048.9 1715.67
  5179.1 1716.51  5205.2 1719.13  5231.4 1725.51  5257.6 1724.66  5292.5 1727.69
  5341.3 1728.25  5345.7 1728.28  5505.9 1730.72  5635.5 1734.03  5848.8 1742.20
#Mann=11,-1,0
  4361.8     0.1       0  4755.1    0.07       0  4872.1     0.1       0
  4949.0     0.1       0  4997.7    0.05       0  5011.2     0.1       0
  5048.9    0.07       0  5341.3   0.035       0  5345.7    0.07       0
  5505.9   0.035       0  5635.5    0.07       0
Bank Sta=4997.7,5011.2
Exp/Cntr=0.3,0.1

Type RM Length L Ch R = 1,5445,473,473,473
BEGIN DESCRIPTION:
East Town Creek 5.0
END DESCRIPTION:
XS GIS Cut Line= 3
      1923625.01     13945874.99      1923125.00     13946375.00
      1922675.01     13946974.98
#Sta/Elev= 30
  4296.8 1910.63  4330.2 1903.82  4368.4 1892.71  4474.6 1854.66  4517.2 1842.56
  4550.8 1830.74  4597.8 1811.21  4614.4 1801.47  4637.9 1789.94  4665.7 1780.08
  4678.4 1773.93  4716.6 1763.92  4754.4 1752.18  4780.3 1741.41  4805.4 1739.76
  4869.0 1715.06  4879.2 1714.83  4879.7 1714.33  4892.7 1714.83  5000.9 1715.18
  5012.5 1718.38  5040.1 1718.50  5129.9 1718.80  5184.9 1725.90  5260.7 1725.44
  5389.9 1726.15  5589.7 1732.50  5688.5 1735.70  5736.2 1740.02  5753.9 1740.23
#Mann=6,-1,0
  4296.8     0.1       0  4879.2    0.05       0  4892.7     0.1       0
  5040.1    0.07       0  5260.7   0.035       0  5589.7    0.07       0
Bank Sta=4879.2,4892.7
Exp/Cntr=0.3,0.1

Type RM Length L Ch R = 1,4972,902,902,902
BEGIN DESCRIPTION:
East Town Creek 4.0
END DESCRIPTION:
XS GIS Cut Line= 3
      1923325.03     13945674.97      1922725.00     13946275.00
      1922725.00     13946575.02
#Sta/Elev= 30
  4158.9 1907.36  4209.3 1890.68  4301.6 1854.15  4382.2 1827.90  4437.3 1808.78
  4472.3 1795.16  4513.7 1783.49  4595.4 1765.41  4611.3 1760.62  4641.0 1753.55
  4674.9 1740.90  4717.3 1731.41  4738.6 1725.01  4768.2 1723.68  4803.3 1718.87
  4831.9 1716.73  4866.9 1715.93  4892.8 1712.40  4904.0 1710.91  4917.8 1706.94
  4936.4 1706.89  4957.6 1708.83  4981.4 1707.09  4986.3 1705.34  4986.8 1704.84
  4999.9 1705.34  5033.3 1714.69  5060.7 1717.97  5111.3 1721.50  5307.5 1726.37
#Mann=5,-1,0
  4158.9     0.1       0  4611.3    0.07       0  4892.8   0.035       0
  4986.3   0.035       0  4999.9   0.035       0
Bank Sta=4986.3,4999.9
Exp/Cntr=0.3,0.1

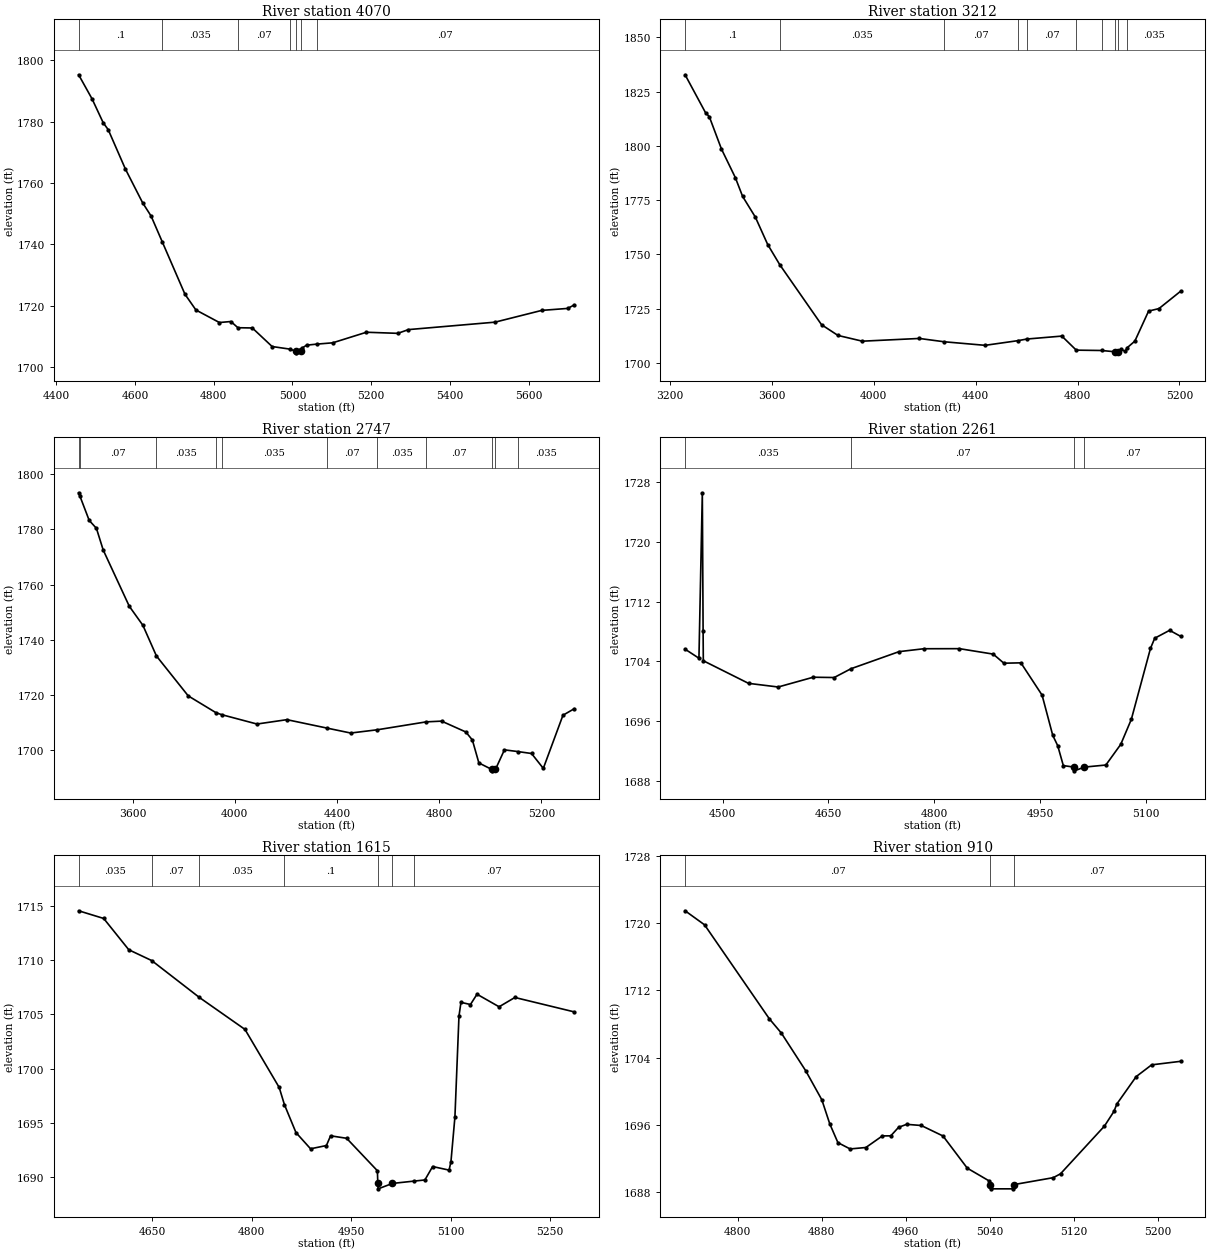
Type RM Length L Ch R = 1,4070,858,858,858
BEGIN DESCRIPTION:
East Town Creek 3.1
END DESCRIPTION:
XS GIS Cut Line= 4
      1922478.45     13945242.21      1922182.90     13945581.46
      1922239.60     13946218.98      1922309.06     13946372.75
#Sta/Elev= 30
  4456.9 1795.20  4491.1 1787.34  4519.4 1779.57  4532.0 1777.36  4575.8 1764.51
  4619.5 1753.55  4641.0 1749.24  4669.5 1740.80  4727.0 1723.81  4754.8 1718.69
  4814.5 1714.61  4843.6 1714.94  4861.5 1712.92  4898.1 1712.84  4948.4 1706.80
  4994.6 1705.94  5007.8 1705.25  5008.3 1704.75  5021.4 1705.25  5023.7 1706.23
  5035.7 1707.24  5061.3 1707.58  5102.2 1708.01  5187.9 1711.45  5267.6 1711.09
  5294.7 1712.31  5514.6 1714.73  5633.4 1718.56  5699.2 1719.20  5715.6 1720.33
#Mann=7,-1,0
  4456.9     0.1       0  4669.5   0.035       0  4861.5    0.07       0
  4994.6   0.033       0  5007.8   0.033       0  5021.4   0.033       0
  5061.3    0.07       0
Bank Sta=5007.8,5021.4
Exp/Cntr=0.3,0.1

Type RM Length L Ch R = 1,3212,465,465,465
BEGIN DESCRIPTION:
East Town Creek 3.0
END DESCRIPTION:
XS GIS Cut Line= 4
      1922564.54     13944867.75      1921686.06     13945709.07
      1921575.00     13946225.00      1921575.00     13946424.99
#Sta/Elev= 30
  3260.4 1832.81  3340.7 1815.31  3355.3 1813.53  3403.1 1798.58  3457.3 1785.47
  3486.1 1776.75  3536.0 1767.22  3584.5 1754.58  3631.9 1745.27  3795.7 1717.63
  3860.1 1712.69  3955.7 1710.04  4179.3 1711.30  4277.0 1709.77  4437.5 1708.13
  4567.1 1710.30  4601.0 1711.03  4738.4 1712.39  4795.0 1705.91  4894.9 1705.75
  4946.1 1705.17  4946.6 1704.67  4960.3 1705.17  4969.3 1706.38  4987.0 1705.32
  4994.8 1707.03  5024.8 1710.05  5078.8 1723.91  5119.4 1725.06  5204.5 1733.07
#Mann=10,-1,0
  3260.4     0.1       0  3631.9   0.035       0  4277.0    0.07       0
  4567.1   0.035       0  4601.0    0.07       0  4795.0   0.033       0
  4894.9     0.1       0  4946.1   0.035       0  4960.3     0.1       0
  4994.8   0.035       0
Bank Sta=4946.1,4960.3
Exp/Cntr=0.3,0.1

Type RM Length L Ch R = 1,2747,486,486,486
BEGIN DESCRIPTION:
East Town Creek 2.0
END DESCRIPTION:
XS GIS Cut Line= 4
      1922457.57     13944832.47      1921767.83     13945584.21
      1921275.00     13945925.00      1921074.97     13946175.03
#Sta/Elev= 30
  3388.9 1793.25  3393.6 1792.13  3430.3 1783.24  3458.5 1780.38  3485.1 1772.52
  3587.2 1752.15  3640.4 1745.26  3693.4 1734.16  3817.9 1719.70  3926.4 1713.62
  3948.5 1712.91  4087.0 1709.51  4204.1 1711.09  4361.0 1708.04  4453.7 1706.25
  4558.1 1707.43  4749.8 1710.30  4809.6 1710.56  4904.5 1706.63  4930.0 1703.73
  4955.5 1695.42  5006.1 1693.06  5006.6 1692.56  5020.3 1693.06  5055.5 1700.16
  5108.1 1699.54  5161.6 1698.84  5207.7 1693.45  5284.6 1712.69  5328.5 1715.04
#Mann=11,-1,0
  3388.9     0.1       0  3393.6    0.07       0  3693.4   0.035       0
  3926.4    0.07       0  3948.5   0.035       0  4361.0    0.07       0
  4558.1   0.035       0  4749.8    0.07       0  5006.1    0.05       0
  5020.3    0.07       0  5108.1   0.035       0
Bank Sta=5006.1,5020.3
Exp/Cntr=0.3,0.1

Type RM Length L Ch R = 1,2261,646,646,646
BEGIN DESCRIPTION:
East Town Creek 1.3
END DESCRIPTION:
XS GIS Cut Line= 3
      1921802.63     13945272.34      1921501.86     13945497.49
      1921176.83     13945472.49
#Sta/Elev= 30
  4447.0 1705.62  4466.6 1704.41  4471.4 1726.59  4472.5 1708.06  4472.8 1704.07
  4536.8 1701.04  4578.8 1700.55  4628.4 1701.86  4658.1 1701.82  4681.9 1703.00
  4749.9 1705.29  4785.1 1705.68  4835.5 1705.69  4883.3 1704.96  4898.4 1703.74
  4922.5 1703.79  4952.5 1699.46  4967.6 1694.07  4974.6 1692.69  4982.6 1690.01
  4997.9 1689.81  4998.4 1689.31  5012.2 1689.81  5042.8 1690.09  5063.9 1692.86
  5078.9 1696.22  5106.0 1705.73  5112.0 1707.09  5133.1 1708.15  5148.7 1707.34
#Mann=4,-1,0
  4447.0   0.035       0  4681.9    0.07       0  4997.9    0.05       0
  5012.2    0.07       0
Bank Sta=4997.9,5012.2
Exp/Cntr=0.3,0.1

Type RM Length L Ch R = 1,1615,705,705,705
BEGIN DESCRIPTION:
East Town Creek 1.2
END DESCRIPTION:
XS GIS Cut Line= 3
      1921978.49     13944833.97      1921678.56     13945001.57
      1921278.26     13944950.19
#Sta/Elev= 30
  4539.1 1714.58  4576.9 1713.87  4614.7 1710.98  4649.3 1709.98  4721.2 1706.57
  4789.9 1703.62  4841.5 1698.26  4849.4 1696.67  4866.8 1694.09  4888.8 1692.59
  4912.7 1692.89  4919.0 1693.79  4943.2 1693.56  4989.6 1690.56  4990.2 1689.39
  4990.7 1688.89  5012.3 1689.39  5044.1 1689.60  5061.2 1689.71  5072.9 1690.95
  5097.7 1690.62  5100.5 1691.40  5106.5 1695.54  5112.6 1704.85  5115.6 1706.12
  5129.9 1705.92  5139.8 1706.87  5173.1 1705.71  5196.9 1706.57  5286.3 1705.24
#Mann=7,-1,0
  4539.1   0.035       0  4649.3    0.07       0  4721.2   0.035       0
  4849.4     0.1       0  4990.2    0.05       0  5012.3     0.1       0
  5044.1    0.07       0
Bank Sta=4990.2,5012.3
Exp/Cntr=0.3,0.1

Type RM Length L Ch R = 1,910,392,392,392
BEGIN DESCRIPTION:
East Town Creek 1.1
END DESCRIPTION:
XS GIS Cut Line= 3
      1921690.11     13944239.52      1921478.12     13944503.80
      1921348.40     13944531.82
#Sta/Elev= 30
  4750.1 1721.48  4768.6 1719.81  4830.2 1708.63  4841.7 1706.92  4864.8 1702.45
  4880.2 1698.98  4887.8 1696.10  4895.5 1693.88  4907.1 1693.13  4922.1 1693.30
  4937.8 1694.68  4945.8 1694.69  4953.2 1695.70  4960.9 1696.06  4974.8 1695.92
  4995.5 1694.67  5018.6 1690.84  5039.7 1689.30  5040.4 1688.88  5040.9 1688.38
  5062.2 1688.38  5062.7 1688.88  5100.4 1689.71  5107.3 1690.17  5149.1 1695.85
  5158.1 1697.59  5161.0 1698.50  5179.3 1701.74  5194.0 1703.14  5221.6 1703.56
#Mann=3,-1,0
  4750.1    0.07       0  5040.4    0.05       0  5062.7    0.07       0
Bank Sta=5040.4,5062.7
Exp/Cntr=0.3,0.1

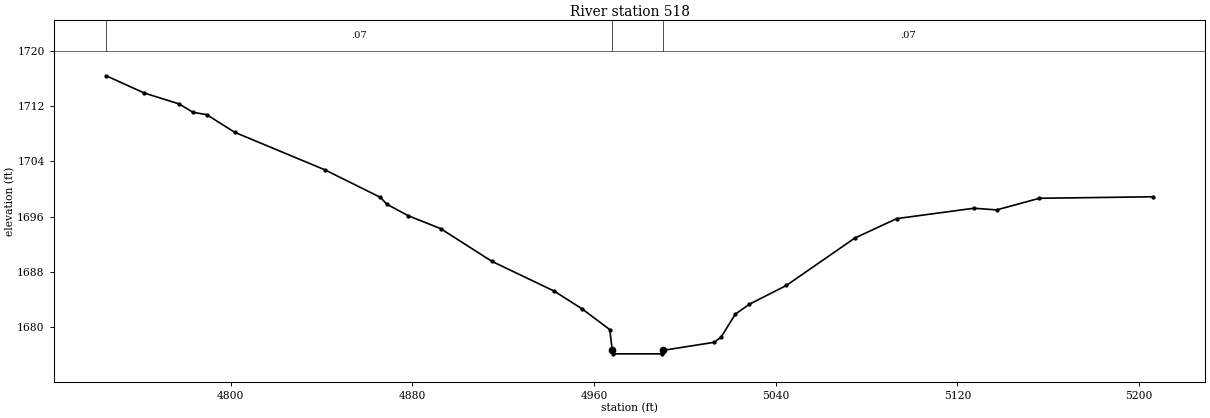
Type RM Length L Ch R = 1,518,0,0,0
BEGIN DESCRIPTION:
East Town Creek 1.0
END DESCRIPTION:
XS GIS Cut Line= 3
      1921575.00     13944125.00      1921325.00     13944175.00
      1921125.00     13944225.00
#Sta/Elev= 30
  4745.1 1716.40  4761.9 1713.90  4777.2 1712.33  4783.3 1711.12  4789.4 1710.77
  4801.7 1708.22  4841.5 1702.78  4865.9 1698.80  4868.7 1697.81  4878.2 1696.14
  4892.4 1694.28  4914.9 1689.56  4942.4 1685.24  4954.7 1682.67  4966.9 1679.67
  4968.0 1676.66  4968.5 1676.16  4989.8 1676.16  4990.3 1676.66  5012.9 1677.83
  5016.0 1678.61  5022.2 1681.90  5028.4 1683.34  5044.7 1686.06  5074.8 1692.91
  5093.3 1695.73  5127.3 1697.23  5137.3 1696.99  5156.1 1698.67  5206.2 1698.89
#Mann=3,-1,0
  4745.1    0.07       0  4968.0    0.05       0  4990.3    0.07       0
Bank Sta=4968,4990.3
Exp/Cntr=0.3,0.1

Chan Stop Cuts=-1