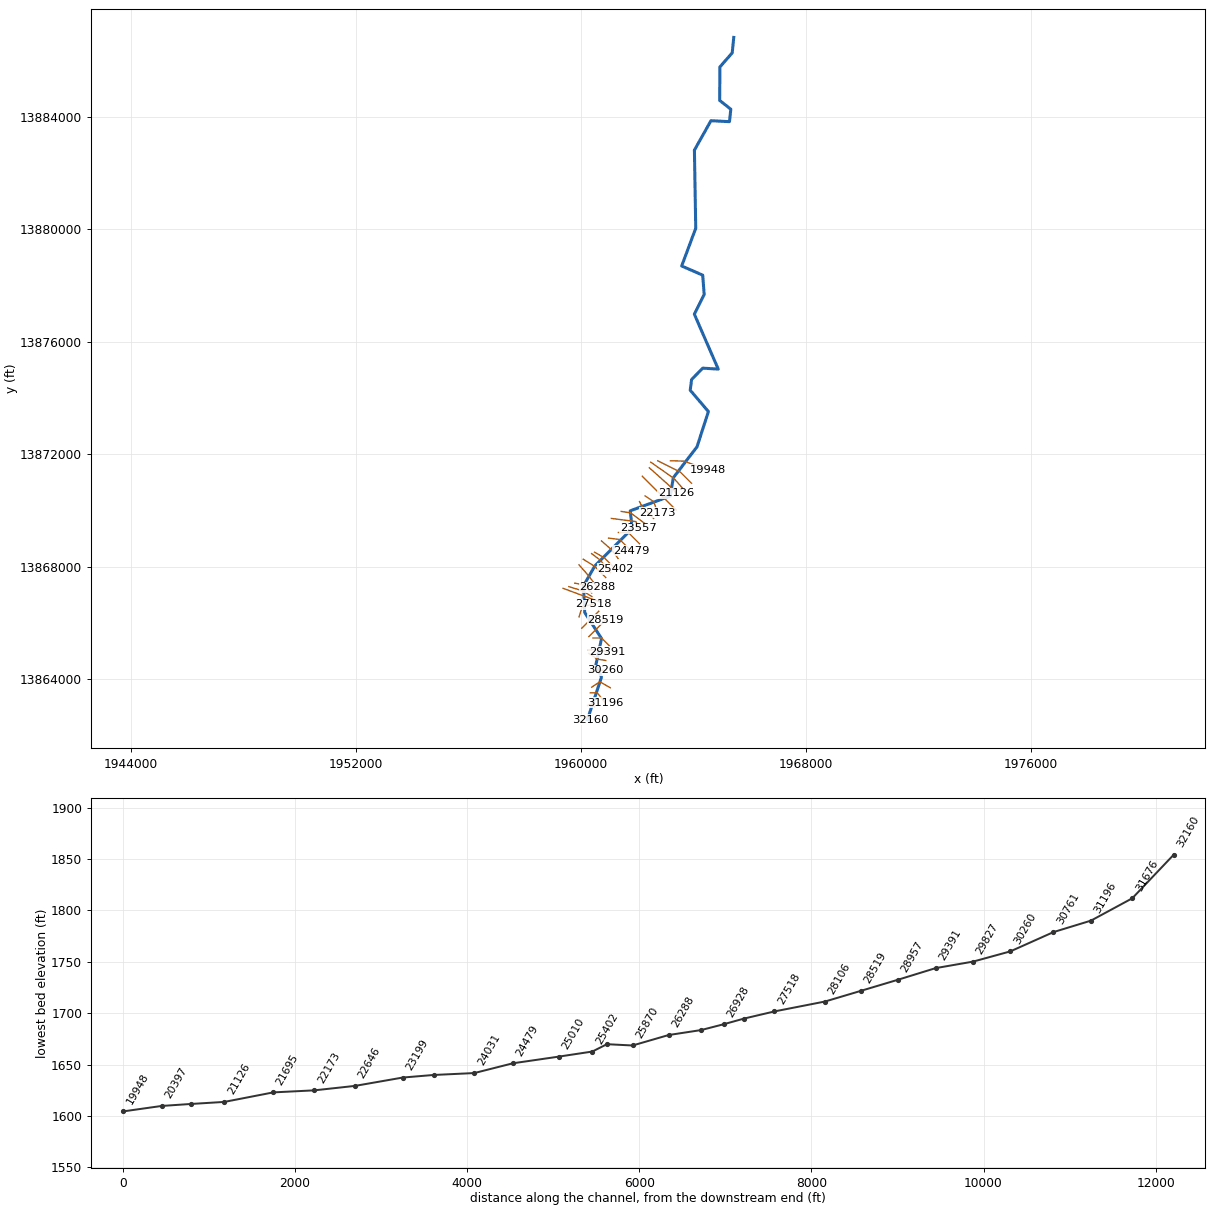
--- Elm Creek.prj (project) ---

Proj Title=Elm Creek Base Level Engineering
Current Plan=p01
Default Exp/Contr=0.3,0.1
English Units
Geom File=g01
Flow File=f01
Plan File=p01
Y Axis Title=Elevation
X Axis Title(PF)=Main Channel Distance
X Axis Title(XS)=Station
BEGIN DESCRIPTION:
Elm Creek
END DESCRIPTION:
DSS Export Rating Curves= 0
DSS Export Rating Curve Sorted= 0
DSS Export Volume Flow Curves= 0
DXF OffsetX= 0
DXF OffsetY= 0
DXF ScaleX= 1
DXF ScaleY= 10

--- Elm Creek.p01 (plan) ---

Plan Title=Multiple Run
Short Identifier=Multiple
Geom File=g01
Flow File=f01
Subcritical Flow
K Sum by GR= 0
Std Step Tol= 0.01
Critical Tol= 0.01
Num of Std Step Trials= 20
Max Error Tol= 0.3
Flow Tol Ratio= 0.001
Split Flow NTrial= 30
Split Flow Tol= 0.02
Split Flow Ratio= 0.02
Log Output Level= 0
Friction Slope Method= 1
Unsteady Friction Slope Method= 2
Unsteady Bridges Friction Slope Method= 1
Parabolic Critical Depth
Global Vel Dist=  1 , 1 , 1
Global Log Level= 0
CheckData=True
Encroach Param= -1, 0, 0, 0
BEGIN DESCRIPTION:
Multiple Run
END DESCRIPTION:

--- Elm Creek.f01 (steady flow) ---

Flow Title=Multiple
Program Version=4.10
Number of Profiles= 7
Profile Names=10-year,25-year,50-year,1pct_min,100-year,1pct_plu,500-year
River Rch & RM=Elm Creek,Reach-1         ,32160
     137     200     252     155     310     618     458
River Rch & RM=Elm Creek,Reach-1         ,31676
    1118    1914    2678    1816    3623    7228    6536
River Rch & RM=Elm Creek,Reach-1         ,26928
    1830    3231    4613    3185    6356   12681   11911
River Rch & RM=Elm Creek,Reach-1         ,26288
    2218    3942    5653    3914    7810   15583   14729
River Rch & RM=Elm Creek,Reach-1         ,22646
    2990    5383    7784    5428   10831   21610   20726
River Rch & RM=Elm Creek,Reach-1         ,19649
    3434    6223    9038    6328   12626   25191   24355
River Rch & RM=Elm Creek,Reach-1         ,19046
    3754    6820    9922    6955   13876   27687   26834
River Rch & RM=Elm Creek,Reach-1         ,17418
    4016    7309   10645    7467   14898   29725   28852
River Rch & RM=Elm Creek,Reach-1         ,14636
    4182    7610   11080    7768   15500   30926   29989
River Rch & RM=Elm Creek,Reach-1         ,12235
    4748    8677   12670    8904   17766   35447   34537
River Rch & RM=Elm Creek,Reach-1         ,9645
    4847    8858   12934    9087   18132   36177   35236
River Rch & RM=Elm Creek,Reach-1         ,7797
    5000    9139   13344    9375   18705   37322   36345
River Rch & RM=Elm Creek,Reach-1         ,5963
    5144    9407   13740    9655   19264   38436   37443
River Rch & RM=Elm Creek,Reach-1         ,4551
    5463   10002   14621   10279   20508   40920   39900
Boundary for River Rch & Prof#=Elm Creek,Reach-1         , 1
Up Type= 0
Dn Type= 3
Dn Slope=0.007
Boundary for River Rch & Prof#=Elm Creek,Reach-1         , 2
Up Type= 0
Dn Type= 3
Dn Slope=0.007
Boundary for River Rch & Prof#=Elm Creek,Reach-1         , 3
Up Type= 0
Dn Type= 3
Dn Slope=0.007
Boundary for River Rch & Prof#=Elm Creek,Reach-1         , 4
Up Type= 0
Dn Type= 3
Dn Slope=0.007
Boundary for River Rch & Prof#=Elm Creek,Reach-1         , 5
Up Type= 0
Dn Type= 3
Dn Slope=0.007
Boundary for River Rch & Prof#=Elm Creek,Reach-1         , 6
Up Type= 0
Dn Type= 3
Dn Slope=0.007
Boundary for River Rch & Prof#=Elm Creek,Reach-1         , 7
Up Type= 0
Dn Type= 3
Dn Slope=0.007
DSS Import GetInterval= 0
DSS Import GetPeak= 0
DSS Import FillOption= 0

--- Elm Creek.g01 (geometry) ---

Geom Title=Existing Conditions
Program Version=4.10

River Reach=Elm Creek       ,Reach-1
Reach XY= 30
        1960225.       13862575.      1960724.28     13864085.71
      1960524.19     13864519.97      1960725.28     13865454.82
      1960127.23     13866380.93      1960083.07     13867328.31
      1960488.63     13868038.21      1961816.86     13869368.94
      1961744.42     13869995.54      1963166.87     13870518.92
      1963278.46     13871173.51      1964119.66     13872272.49
        1964525.       13873525.      1963878.06     13874283.28
      1963926.74     13874663.13      1964321.66      13875067.4
       1964874.3     13875034.77      1964025.27     13876985.68
      1964373.95     13877685.43      1964321.57     13878373.77
       1963574.5     13878700.03      1964074.48     13880040.22
      1964027.24     13882819.07      1964615.21     13883864.57
      1965273.02     13883830.67      1965321.47     13884273.54
      1964926.05     13884585.43      1964932.53     13885774.99
      1965371.39      13886276.5        1965425.       13886825.

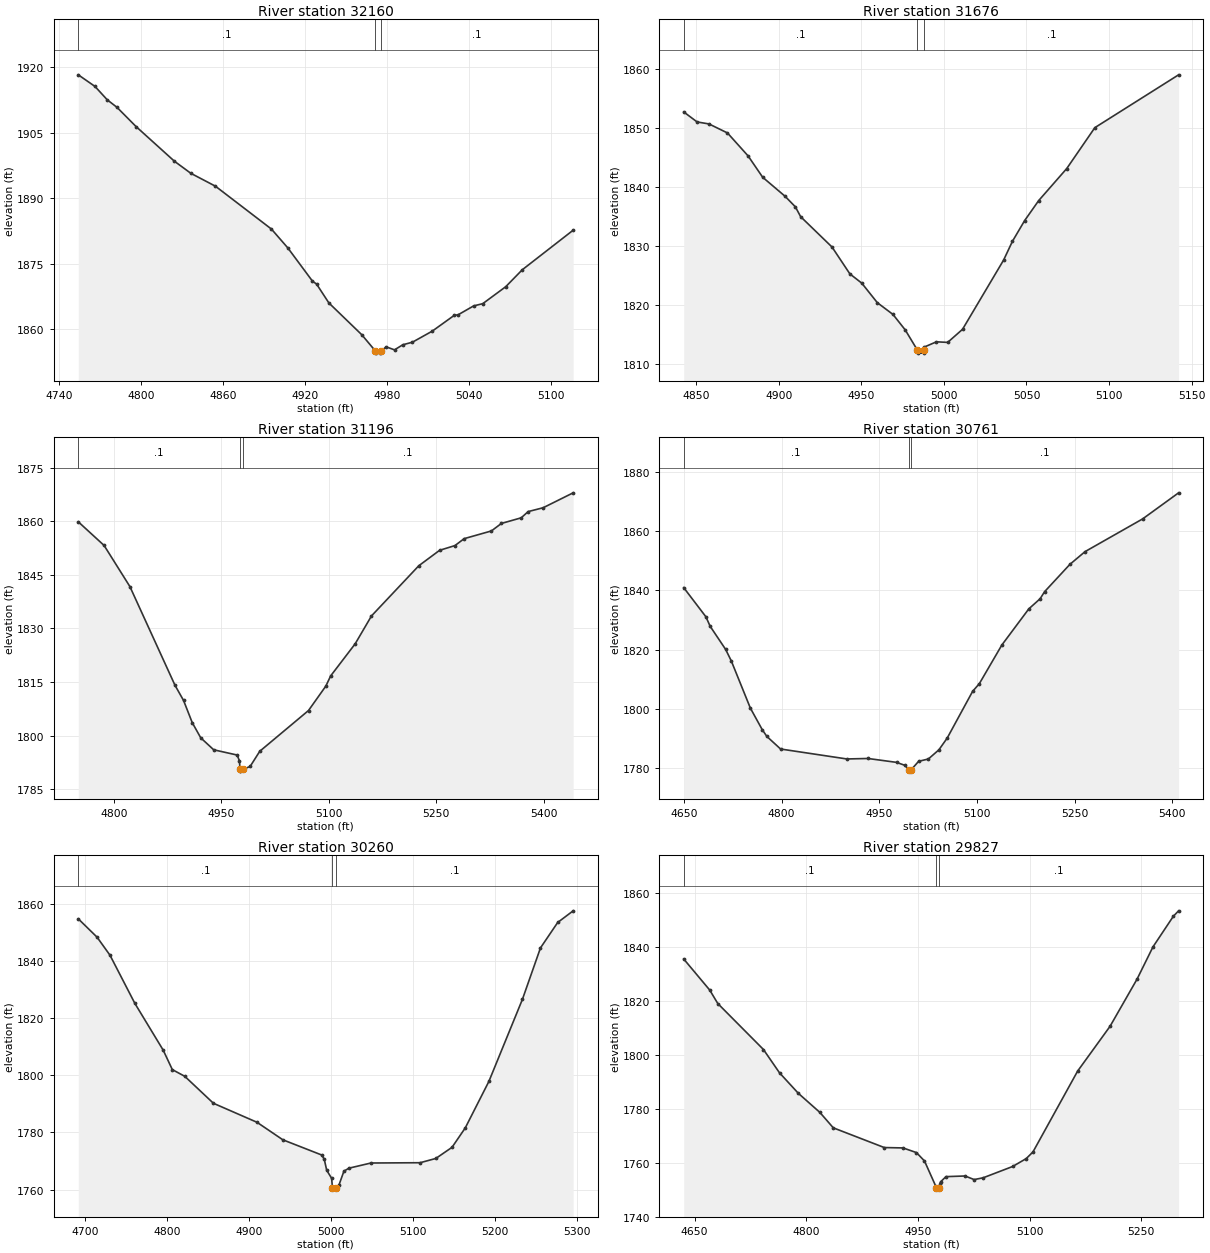
Type RM Length L Ch R = 1 ,32160   ,484,484,484
BEGIN DESCRIPTION:
Elm Creek 65.0
END DESCRIPTION:
XS GIS Cut Line= 3
      1960024.96       13862675.        1960275.       13862675.
      1960324.98     13862575.04
#Sta/Elev= 30
  4754.3  1918.3  4766.5 1915.64  4775.5 1912.56  4782.6 1910.84  4796.5 1906.44
  4824.6 1898.47  4836.6  1895.7  4854.6 1892.74  4895.5 1882.91  4907.5 1878.58
  4925.5 1870.96  4928.5 1870.29  4937.5 1865.96  4961.5 1858.68  4971.5 1854.94
  4971.7 1854.44  4975.2 1854.44  4975.5 1854.94  4979.5 1855.87  4985.5 1855.19
  4991.5 1856.35  4998.6 1856.95  5013.1 1859.49  5029.3 1863.14  5031.9 1863.22
  5043.3 1865.27    5050 1865.79  5066.8 1869.68  5078.9 1873.57  5116.1 1882.65
#Mann= 3 ,-1 , 0
  4754.3      .1       0  4971.5     .05       0  4975.5      .1       0
Bank Sta=4971.5,4975.5
XS Rating Curve= 0 ,0
Exp/Cntr=0.3,0.1

Type RM Length L Ch R = 1 ,31676   ,480,480,480
BEGIN DESCRIPTION:
Elm Creek 64.0
END DESCRIPTION:
XS GIS Cut Line= 3
      1960224.97     13863074.99        1960375.       13863125.
      1960475.03     13863024.97
#Sta/Elev= 30
  4842.5 1852.73  4850.6 1851.03  4857.8 1850.69    4869 1849.16  4881.5 1845.26
  4890.3 1841.65  4903.8 1838.44  4910.1 1836.63  4913.3 1834.96  4932.3 1829.81
  4943.1 1825.26  4950.3 1823.69  4959.7 1820.38  4969.2 1818.38  4976.6 1815.76
    4984 1812.32  4984.3 1811.82  4987.8 1811.82    4988 1812.32  4988.2 1812.86
  4995.5 1813.74  5002.3 1813.64  5011.3 1815.86  5036.2 1827.62  5041.5 1830.78
  5048.9  1834.3  5057.4 1837.69  5074.4 1843.13  5091.4 1850.06  5142.1 1859.02
#Mann= 3 ,-1 , 0
  4842.5      .1       0    4984     .05       0    4988      .1       0
Bank Sta=4984,4988
XS Rating Curve= 0 ,0
Exp/Cntr=0.3,0.1

Type RM Length L Ch R = 1 ,31196   ,435,435,435
BEGIN DESCRIPTION:
Elm Creek 63.0
END DESCRIPTION:
XS GIS Cut Line= 3
      1960325.02       13863525.        1960575.       13863525.
      1960846.88     13863177.12
#Sta/Elev= 30
  4749.9 1859.83    4786 1853.21    4822 1841.72    4885 1814.11    4897 1809.85
  4909.1 1803.66    4921  1799.4  4939.1 1796.05  4971.9 1794.58    4975    1793
    4976 1790.58  4976.3 1790.08    4980 1790.58    4990 1791.38  5003.5 1795.64
  5071.6 1807.04  5095.9  1813.9  5102.5 1816.71  5136.8  1825.7  5159.6  1833.5
  5225.7 1847.54  5254.8 1851.86  5276.2 1853.18  5289.1 1855.12  5327.2 1857.28
  5341.1 1859.37  5368.8 1860.95  5378.5 1862.69  5399.5 1863.77  5441.4 1867.94
#Mann= 3 ,-1 , 0
  4749.9      .1       0    4976     .05       0    4980      .1       0
Bank Sta=4976,4980
XS Rating Curve= 0 ,0
Exp/Cntr=0.3,0.1

Type RM Length L Ch R = 1 ,30761   ,501,501,501
BEGIN DESCRIPTION:
Elm Creek 62.0
END DESCRIPTION:
XS GIS Cut Line= 4
        1960375.       13863725.      1960624.66     13863891.44
      1960706.92     13863893.08      1961035.05     13863706.71
#Sta/Elev= 30
  4649.8 1840.92  4683.9 1831.06  4690.4 1827.86  4714.2 1820.04  4722.8 1816.19
  4752.1 1800.24  4770.2    1793  4777.4 1790.67  4798.5 1786.41  4900.2 1783.05
  4932.7 1783.21  4976.5  1781.9  4989.4 1780.89  4995.1 1779.44  4995.3 1778.94
  4999.1 1779.44  5010.4 1782.25  5025.4 1783.04  5041.6 1786.15  5054.3 1790.11
  5093.3 1805.88  5103.7 1808.51  5138.2 1821.54  5179.6 1833.75  5196.9 1837.16
  5203.8 1839.55  5242.6 1848.77  5265.9 1853.08  5354.3 1864.13  5409.5 1872.94
#Mann= 3 ,-1 , 0
  4649.8      .1       0  4995.1     .05       0  4999.1      .1       0
Bank Sta=4995.1,4999.1
XS Rating Curve= 0 ,0
Exp/Cntr=0.3,0.1

Type RM Length L Ch R = 1 ,30260   ,433,433,433
BEGIN DESCRIPTION:
Elm Creek 61.0
END DESCRIPTION:
XS GIS Cut Line= 3
      1960274.95     13864274.99        1960575.       13864325.
      1960875.01       13864325.
#Sta/Elev= 30
  4691.2 1854.76  4714.1 1848.35  4729.9 1842.03  4760.3 1825.16  4794.9 1808.79
    4806    1802  4821.2 1799.65  4856.2 1790.21  4909.4 1783.56  4940.9 1777.44
  4988.4 1772.11  4991.5 1770.64  4994.5 1766.77  5000.5 1763.96  5001.5 1760.67
  5001.8 1760.17  5005.5 1760.67  5009.5 1761.64  5015.5 1766.44  5021.5 1767.49
  5048.5 1769.31  5108.5 1769.41  5127.7  1770.9  5147.5  1774.8  5163.7 1781.61
  5192.5 1797.86  5233.4 1826.55  5255.5 1844.59  5276.5 1853.48  5295.4 1857.56
#Mann= 3 ,-1 , 0
  4691.2      .1       0  5001.5     .05       0  5005.5      .1       0
Bank Sta=5001.5,5005.5
XS Rating Curve= 0 ,0
Exp/Cntr=0.3,0.1

Type RM Length L Ch R = 1 ,29827   ,436,436,436
BEGIN DESCRIPTION:
Elm Creek 60.0
END DESCRIPTION:
XS GIS Cut Line= 3
      1960275.03     13864924.98        1960575.       13864725.
      1960875.05     13864674.99
#Sta/Elev= 30
  4635.4 1835.51  4670.4 1823.97  4681.2 1818.99  4742.5 1801.96  4764.1 1793.31
  4789.4 1785.71  4818.2 1778.67  4836.3 1772.93  4904.8 1765.62    4930 1765.48
    4948 1763.75  4958.8 1760.65  4974.9 1750.71  4975.1 1750.21  4978.9 1750.71
  4979.5 1752.23  4980.5 1752.94  4987.7 1754.84  5013.3 1755.08  5025.5 1753.75
  5037.6 1754.41  5077.2  1758.6  5095.4 1761.52  5104.5 1763.99  5164.5 1793.96
    5208 1810.54  5244.4 1828.09  5265.7    1840  5293.1 1851.36  5300.1 1853.36
#Mann= 3 ,-1 , 0
  4635.4      .1       0  4974.9     .05       0  4978.9      .1       0
Bank Sta=4974.9,4978.9
XS Rating Curve= 0 ,0
Exp/Cntr=0.3,0.1

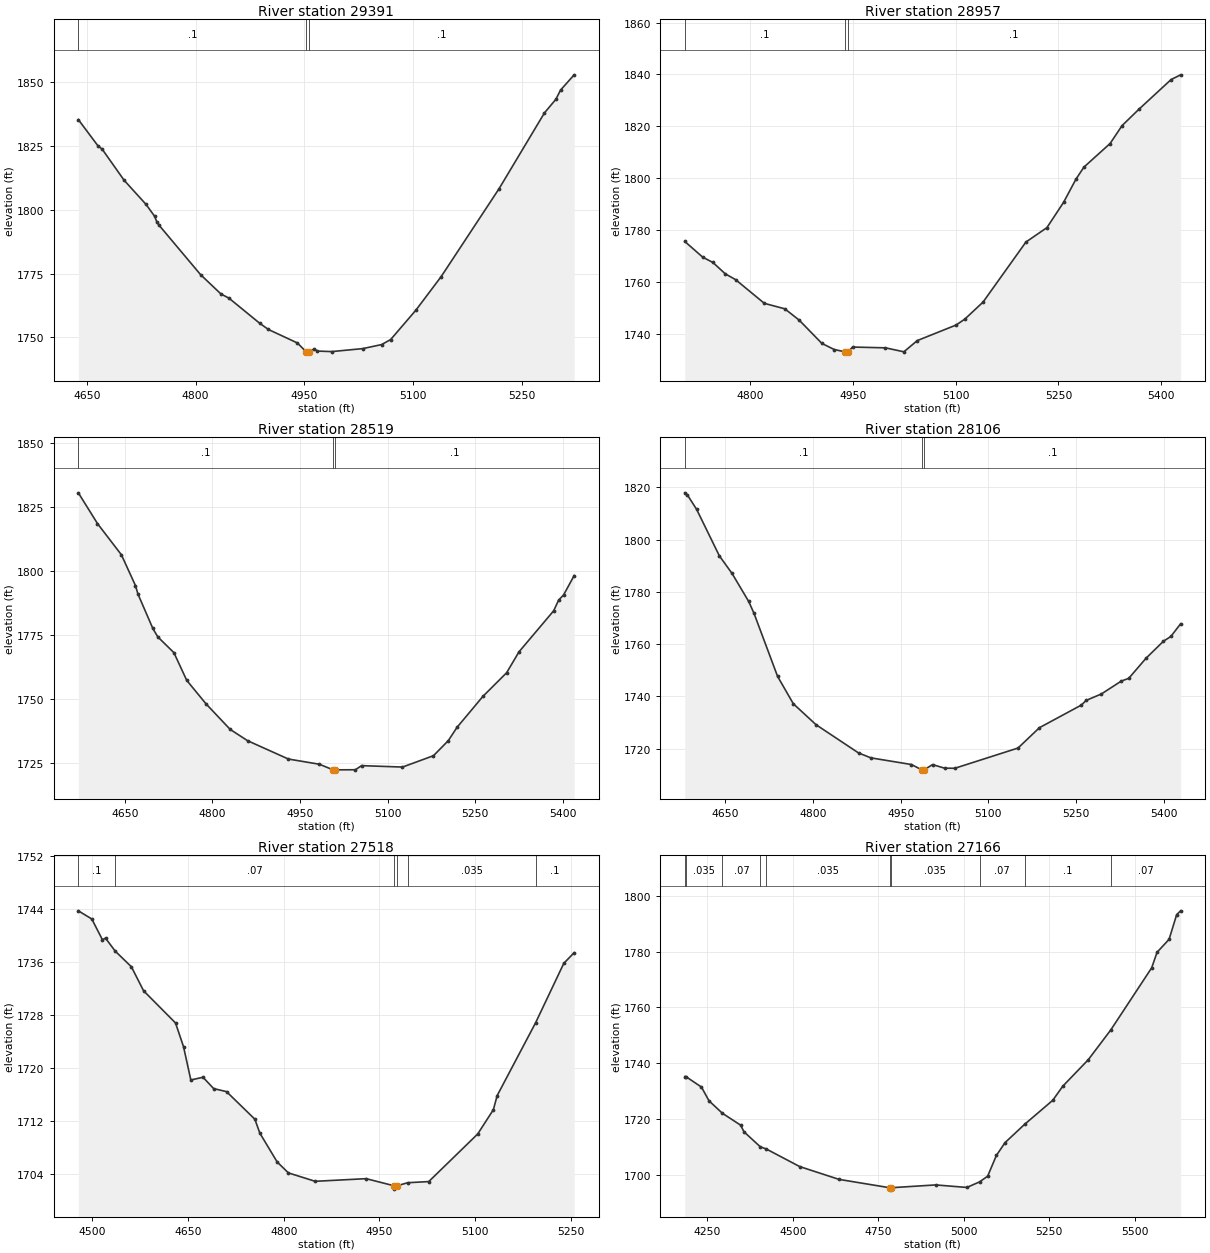
Type RM Length L Ch R = 1 ,29391   ,434,434,434
BEGIN DESCRIPTION:
Elm Creek 59.0
END DESCRIPTION:
XS GIS Cut Line= 3
      1960259.27     13865043.12        1960625.       13865075.
      1960924.96     13864975.01
#Sta/Elev= 30
  4638.4 1835.25  4665.4 1824.99  4671.3 1823.65  4701.5  1811.5  4731.6 1802.09
  4743.7 1797.34  4746.7 1795.07  4749.7 1793.89  4806.9 1774.55  4834.9 1767.01
    4846 1765.36  4888.2 1755.57  4900.3 1753.11  4940.2 1747.84  4952.5 1744.35
  4952.7 1743.85  4956.5 1744.35  4963.5 1745.49  4967.9 1744.65  4987.6 1744.45
  5030.4 1745.62  5056.3 1747.19  5068.8 1749.16  5103.7  1760.7  5138.5 1773.83
  5218.2 1808.19  5280.8 1837.88  5296.6 1843.22  5302.9 1846.78  5321.7 1852.76
#Mann= 3 ,-1 , 0
  4638.4      .1       0  4952.5     .05       0  4956.5      .1       0
Bank Sta=4952.5,4956.5
XS Rating Curve= 0 ,0
Exp/Cntr=0.3,0.1

Type RM Length L Ch R = 1 ,28957   ,438,438,438
BEGIN DESCRIPTION:
Elm Creek 58.0
END DESCRIPTION:
XS GIS Cut Line= 3
      1960425.04       13865475.        1960725.       13865475.
      1961024.98     13865175.02
#Sta/Elev= 30
  4704.3 1775.65  4730.5  1769.6  4745.4 1767.55  4763.4 1763.19  4778.4 1760.96
  4820.5 1751.81  4850.4  1749.7  4871.4 1745.34  4904.5 1736.38  4922.5 1734.02
  4938.4 1733.13  4938.7 1732.63  4942.4 1733.13  4949.5 1734.97  4997.4 1734.67
  5024.3 1733.14  5043.9 1737.47  5100.6 1743.46  5113.4 1745.76  5139.9 1752.29
  5202.5 1775.42  5233.2 1780.98  5257.6 1790.75  5275.6 1799.65  5287.3 1804.31
  5325.5  1813.4    5343  1820.3  5367.9 1826.68  5414.6 1838.04  5428.5 1839.86
#Mann= 3 ,-1 , 0
  4704.3      .1       0  4938.4     .05       0  4942.4      .1       0
Bank Sta=4938.4,4942.4
XS Rating Curve= 0 ,0
Exp/Cntr=0.3,0.1

Type RM Length L Ch R = 1 ,28519   ,413,413,413
BEGIN DESCRIPTION:
Elm Creek 57.0
END DESCRIPTION:
XS GIS Cut Line= 3
      1960274.98     13865524.98        1960575.       13865825.
      1960875.03     13866125.03
#Sta/Elev= 30
  4570.6 1830.51  4603.4 1818.47  4644.3 1806.27  4668.4 1794.22  4672.6 1790.93
  4698.1 1777.46  4706.6 1774.16  4734.2 1767.98  4756.1 1757.16  4789.3 1747.92
  4830.5 1737.96  4860.2 1733.55  4930.1 1726.37  4983.2 1724.33  5006.7 1722.14
  5006.9 1721.64  5010.7 1722.14  5044.8 1722.18  5055.4 1723.79  5125.4 1723.23
  5178.4 1727.67  5203.9 1733.59  5218.6 1738.73  5263.3 1750.95  5303.6 1760.12
  5324.8 1768.31  5384.1 1784.36  5392.7 1788.57  5401.1 1790.56  5419.2 1798.14
#Mann= 3 ,-1 , 0
  4570.6      .1       0  5006.7     .05       0  5010.7      .1       0
Bank Sta=5006.7,5010.7
XS Rating Curve= 0 ,0
Exp/Cntr=0.3,0.1

Type RM Length L Ch R = 1 ,28106   ,588,588,588
BEGIN DESCRIPTION:
Elm Creek 56.0
END DESCRIPTION:
XS GIS Cut Line= 3
      1960024.97     13865824.97        1960325.       13866125.
      1960625.02     13866425.02
#Sta/Elev= 30
  4580.5 1817.91  4585.1 1817.05  4600.8 1811.56  4639.6  1793.8  4661.4 1787.03
  4689.9  1776.3    4699 1771.74  4739.3 1747.63  4766.2 1737.16  4805.1 1729.13
  4877.8 1718.32    4899 1716.43  4968.4 1713.88  4986.1 1711.85  4986.4 1711.35
  4990.1 1711.85  5004.5 1713.85    5025 1712.49  5042.6 1712.44  5150.8 1720.19
  5187.5 1727.99    5259 1736.62  5267.5 1738.43  5293.6 1740.91  5327.5 1745.82
  5340.3 1746.88    5370  1754.6  5399.7 1761.09  5412.4 1762.92  5429.1 1767.77
#Mann= 3 ,-1 , 0
  4580.5      .1       0  4986.1     .05       0  4990.1      .1       0
Bank Sta=4986.1,4990.1
XS Rating Curve= 0 ,0
Exp/Cntr=0.3,0.1

Type RM Length L Ch R = 1 ,27518   ,352,352,352
BEGIN DESCRIPTION:
Elm Creek 55.0
END DESCRIPTION:
XS GIS Cut Line= 3
      1959925.01     13866225.04      1960041.25     13866591.89
      1960425.02     13866675.01
#Sta/Elev= 30
  4477.9 1743.72    4499 1742.49  4515.7 1739.35  4520.5  1739.6  4535.7 1737.64
  4561.1 1735.27  4580.2 1731.65  4630.3 1726.79  4642.9 1723.19  4654.3 1718.18
  4673.4 1718.59  4690.1 1716.88  4710.3 1716.42  4754.7 1712.26  4762.5 1710.16
  4789.7  1705.8  4807.3 1704.15  4849.3 1702.88  4929.2 1703.28  4973.2  1702.2
  4973.5  1701.7  4977.2  1702.2  4994.6 1702.67  5027.4 1702.84  5104.1 1710.02
  5128.7 1713.69  5134.7 1715.83  5194.9 1726.81  5239.2  1735.8  5255.4  1737.4
#Mann= 6 ,-1 , 0
  4477.9      .1       0  4535.7     .07       0  4973.2    .035       0
  4977.2     .07       0  4994.6    .035       0  5194.9      .1       0
Bank Sta=4973.2,4977.2
XS Rating Curve= 0 ,0
Exp/Cntr=0.3,0.1

Type RM Length L Ch R = 1 ,27166   ,238,238,238
BEGIN DESCRIPTION:
Elm Creek 54.1
END DESCRIPTION:
XS GIS Cut Line= 2
      1959358.92     13867239.66      1960719.95     13866736.96
#Sta/Elev= 30
  4183.9 1735.14  4187.4 1735.12  4232.7 1731.39  4254.6 1726.48  4293.7 1722.01
  4347.3 1717.72  4356.9 1715.37    4405 1709.94  4421.9  1709.2    4520 1702.87
  4635.1 1698.27  4783.4 1695.27  4783.7 1694.77  4787.4 1695.27    4918 1696.28
  5009.3 1695.37  5046.6 1697.38  5070.1 1699.41  5095.7 1706.86  5121.2 1711.48
  5178.6 1718.06  5260.5 1726.63  5290.3 1731.75  5364.3 1741.17  5430.2 1751.85
  5550.1 1774.18  5565.8 1779.75    5601  1784.4  5623.3 1793.28  5634.8 1794.63
#Mann= 10 ,-1 , 0
  4183.9     .07       0  4187.4    .035       0  4293.7     .07       0
    4405      .1       0  4421.9    .035       0  4783.4    .035       0
  4787.4    .035       0  5046.6     .07       0  5178.6      .1       0
  5430.2     .07       0
Bank Sta=4783.4,4787.4
XS Rating Curve= 0 ,0
Exp/Cntr=0.3,0.1

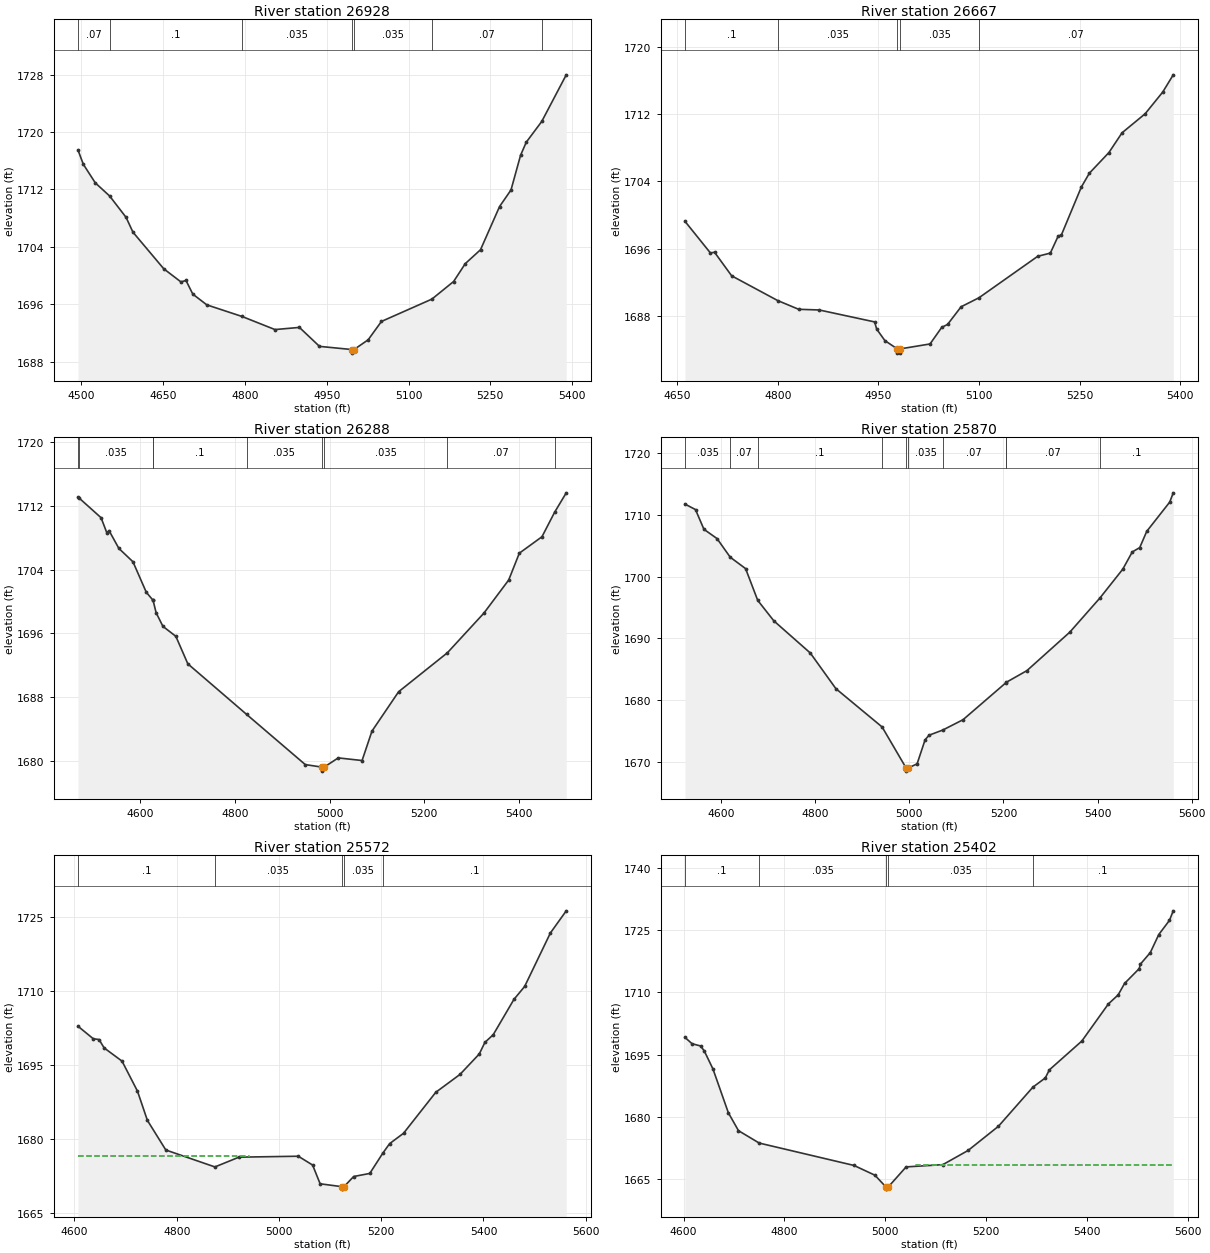
Type RM Length L Ch R = 1 ,26928   ,261,261,261
BEGIN DESCRIPTION:
Mapping XS 2fc5457e
END DESCRIPTION:
XS GIS Cut Line= 3
      1959565.82     13867300.02      1960032.37     13867157.07
       1960382.2     13866948.59
#Sta/Elev= 30
  4493.9 1717.51  4503.7 1715.51  4525.7 1712.92    4552 1711.09  4582.2 1708.11
  4594.7 1706.06  4651.2 1700.96  4682.6 1699.14    4692 1699.33  4704.5 1697.43
  4730.1 1695.94  4794.8 1694.32  4855.1  1692.5  4899.9  1692.8  4936.7 1690.16
    4996 1689.72  4996.2 1689.22    5000 1689.72  5025.9 1691.07  5050.3 1693.63
  5142.8 1696.74  5182.6 1699.19    5204 1701.68  5231.9 1703.61  5266.9 1709.63
  5287.8 1711.93  5305.4 1716.77  5315.8 1718.58  5344.2 1721.47  5389.1 1727.96
#Mann= 7 ,-1 , 0
  4493.9     .07       0    4552      .1       0  4794.8    .035       0
    4996    .035       0    5000    .035       0  5142.8     .07       0
  5344.2      .1       0
Bank Sta=4996,5000
XS Rating Curve= 0 ,0
Exp/Cntr=0.3,0.1

Type RM Length L Ch R = 1 ,26667   ,379,379,379
BEGIN DESCRIPTION:
Elm Creek 54.0
END DESCRIPTION:
XS GIS Cut Line= 3
      1959775.01       13867425.      1960102.59     13867359.29
      1960374.97     13867075.03
#Sta/Elev= 30
  4661.7 1699.24  4699.6 1695.48  4705.8 1695.56  4731.3 1692.76  4799.9 1689.82
  4831.2 1688.78  4861.8  1688.7  4944.4 1687.28  4947.5 1686.42  4959.7 1685.06
  4978.2 1684.07  4978.4 1683.57  4981.9 1683.57  4982.2 1684.07    5027 1684.66
  5044.4 1686.63  5053.1 1686.98  5073.3 1689.08  5099.9 1690.15  5187.5 1695.08
  5206.3 1695.46  5217.8 1697.45  5222.9 1697.64  5252.5 1703.31  5264.5 1704.96
  5293.6 1707.41  5313.2 1709.76  5347.6 1712.02  5373.9 1714.61  5389.5 1716.65
#Mann= 5 ,-1 , 0
  4661.7      .1       0  4799.9    .035       0  4978.2    .035       0
  4982.2    .035       0  5099.9     .07       0
Bank Sta=4978.2,4982.2
XS Rating Curve= 0 ,0
Exp/Cntr=0.3,0.1

Type RM Length L Ch R = 1 ,26288   ,418,418,418
BEGIN DESCRIPTION:
Elm Creek 53.0
END DESCRIPTION:
XS GIS Cut Line= 3
      1959924.99     13868075.01        1960275.       13867675.
      1960574.99     13867275.02
#Sta/Elev= 30
  4468.5 1713.07  4471.6 1712.93  4517.3  1710.5  4529.6 1708.59  4534.1 1708.89
  4554.9 1706.65  4584.7 1704.97  4612.9 1701.14  4626.9 1700.16  4627.2 1700.13
  4633.6 1698.58    4648 1696.87  4675.3 1695.62  4700.6 1692.17  4824.9 1685.82
  4948.7 1679.53  4984.4 1679.21  4984.7 1678.71  4988.5 1679.21  5018.4 1680.37
  5068.7 1680.04  5089.6 1683.73  5145.9 1688.67    5249 1693.56  5325.9 1698.52
  5378.4 1702.68  5400.9 1706.05  5448.7 1708.11  5475.5 1711.19    5500 1713.62
#Mann= 9 ,-1 , 0
  4468.5      .1       0  4471.6    .035       0  4626.9     .07       0
  4627.2      .1       0  4824.9    .035       0  4984.4    .035       0
  4988.5    .035       0    5249     .07       0  5475.5      .1       0
Bank Sta=4984.4,4988.5
XS Rating Curve= 0 ,0
Exp/Cntr=0.3,0.1

Type RM Length L Ch R = 1 ,25870   ,298,298,298
BEGIN DESCRIPTION:
Elm Creek 52.0
END DESCRIPTION:
XS GIS Cut Line= 3
      1960075.01       13868275.        1960475.       13868025.
      1960875.02     13867624.98
#Sta/Elev= 30
  4523.5 1711.75  4545.9 1710.86  4563.8 1707.67  4591.6 1706.17  4619.7 1703.15
  4652.3 1701.31  4678.1 1696.17  4712.4 1692.85  4789.7 1687.66  4844.2 1681.88
  4942.4 1675.68  4993.4 1669.04  4993.6 1668.54  4997.6 1669.04  5016.7 1669.72
  5033.7 1673.61  5042.1 1674.35  5071.3 1675.19  5114.3 1676.86  5204.6 1682.79
  5205.7 1682.89    5250  1684.8  5341.2 1691.03  5405.3 1696.57  5453.7 1701.22
  5473.8    1704  5489.7 1704.71  5504.6 1707.34  5553.4 1712.07  5560.9 1713.57
#Mann= 10 ,-1 , 0
  4523.5    .035       0  4619.7     .07       0  4678.1      .1       0
  4942.4    .035       0  4993.4    .035       0  4997.6    .035       0
  5071.3     .07       0  5204.6    .035       0  5205.7     .07       0
  5405.3      .1       0
Bank Sta=4993.4,4997.6
XS Rating Curve= 0 ,0
Exp/Cntr=0.3,0.1

Type RM Length L Ch R = 1 ,25572   ,170,170,170
BEGIN DESCRIPTION:
Mapping XS 891fab5c
END DESCRIPTION:
XS GIS Cut Line= 3
      1960373.34     13868474.25      1960679.47     13868242.75
      1961042.22      13867801.4
#Sta/Elev= 30
  4606.8 1702.85  4636.7 1700.31    4648 1700.15  4658.1 1698.44    4693 1695.77
  4723.2 1689.69  4742.6 1683.76  4778.7 1677.75  4874.7 1674.32  4921.7  1676.3
  5037.8 1676.49  5065.8  1674.7  5080.5  1670.9  5122.9 1670.32  5123.2 1669.82
  5127.2 1670.32  5146.1 1672.38  5177.6    1673  5203.1 1677.11  5216.4 1679.04
  5243.6 1681.14  5306.7 1689.45    5354 1693.07  5391.8 1697.22  5402.8 1699.57
  5419.1 1701.13  5459.6 1708.29  5480.5  1710.9  5530.9 1721.75  5561.9 1726.24
#Mann= 5 ,-1 , 0
  4606.8      .1       0  4874.7    .035       0  5122.9    .035       0
  5127.2    .035       0  5203.1      .1       0
#XS Ineff= 2 , 0
         4940.66 1676.63
Permanent Ineff=
       F       F
Bank Sta=5122.9,5127.2
XS Rating Curve= 0 ,0
Exp/Cntr=0.3,0.1

Type RM Length L Ch R = 1 ,25402   ,392,392,392
BEGIN DESCRIPTION:
Elm Creek 51.0
END DESCRIPTION:
XS GIS Cut Line= 3
      1960474.96     13868525.02        1960825.       13868325.
      1961224.97     13867925.03
#Sta/Elev= 30
  4602.6 1699.17  4616.7 1697.65  4633.6 1697.11  4640.9 1695.92  4658.2 1691.56
  4688.7 1681.03  4708.8 1676.72  4749.9 1673.74    4938 1668.35  4979.5    1666
  5001.5 1663.15  5001.8 1662.65  5005.8 1663.15  5041.4    1668  5114.2 1668.54
  5164.4 1671.96  5224.5 1677.77  5292.9 1687.19  5317.5 1689.41  5325.7 1691.37
    5390 1698.29  5442.7 1707.23  5462.1  1709.4  5474.8 1712.16  5503.8 1715.72
  5506.3 1716.82  5525.8 1719.57  5542.7 1723.93  5563.9 1727.35  5571.4 1729.64
#Mann= 5 ,-1 , 0
  4602.6      .1       0  4749.9    .035       0  5001.5    .035       0
  5005.8    .035       0  5292.9      .1       0
#XS Ineff= 2 , 0
                         5060.06         1668.55
Permanent Ineff=
       F       F
Bank Sta=5001.5,5005.8
XS Rating Curve= 0 ,0
Exp/Cntr=0.3,0.1

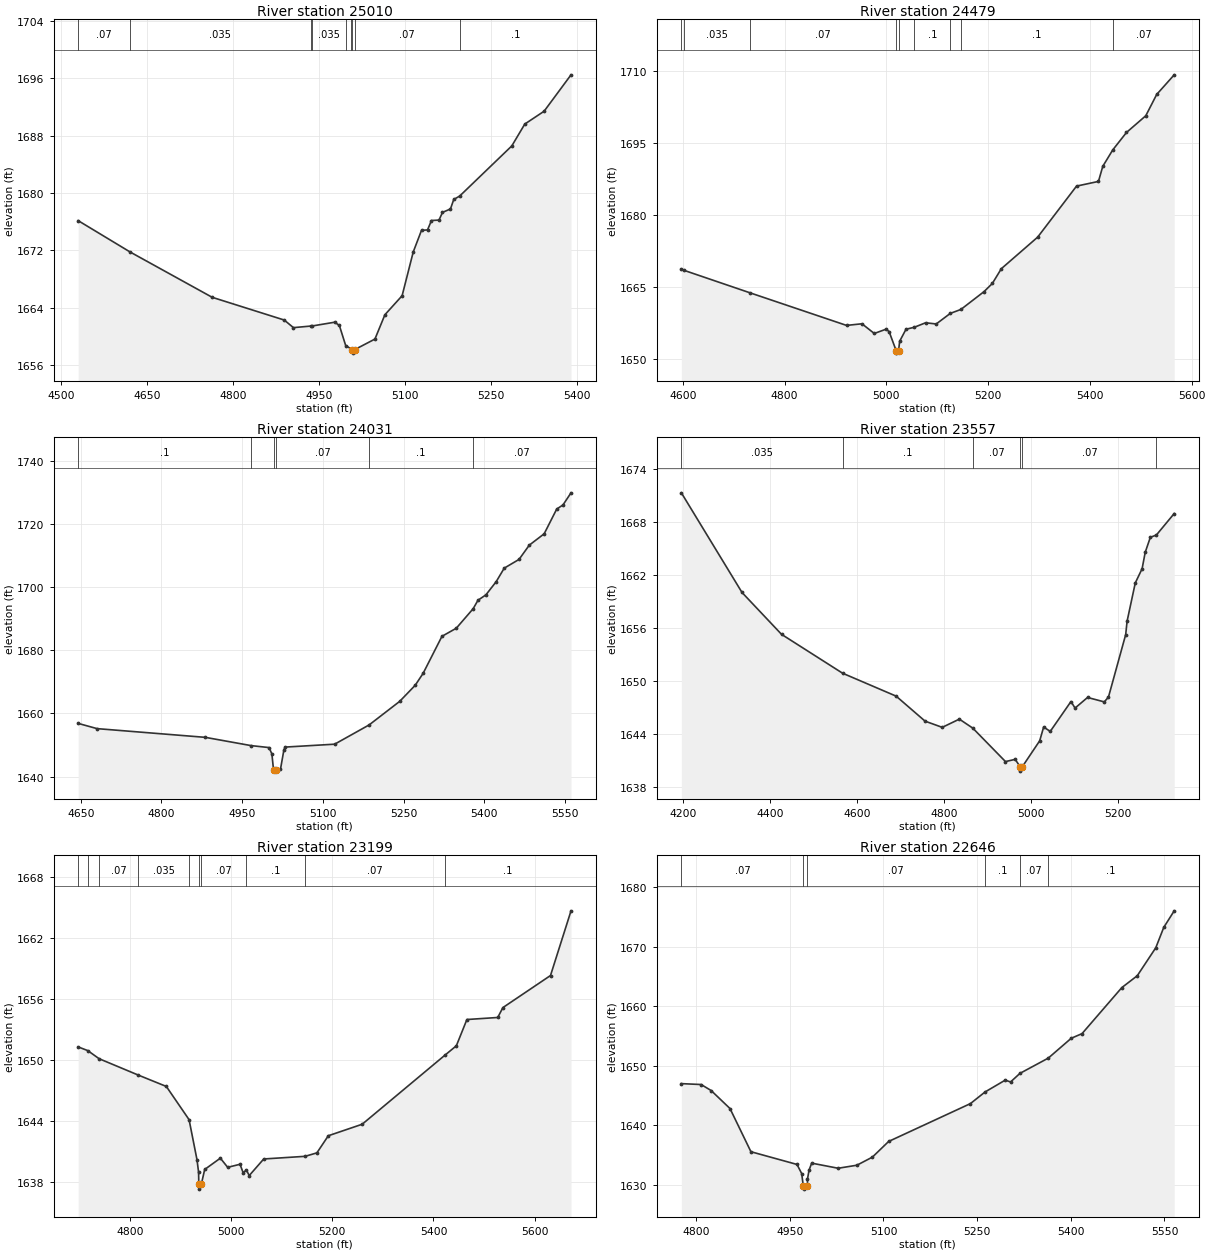
Type RM Length L Ch R = 1 ,25010   ,531,531,531
BEGIN DESCRIPTION:
Elm Creek 50.0
END DESCRIPTION:
XS GIS Cut Line= 3
        1960725.       13868925.      1961084.76     13868606.97
      1961312.43     13868303.82
#Sta/Elev= 30
  4530.4 1676.14    4621 1671.77    4764 1665.46  4889.7 1662.29  4905.7 1661.23
  4935.6 1661.45  4938.9 1661.47  4977.8 1661.99  4985.8 1661.53  4996.8 1658.74
  5006.6 1658.25  5008.4 1658.18  5008.7 1657.68  5012.8 1658.18  5047.8 1659.64
  5065.2 1663.03  5095.2 1665.68  5114.6 1671.78    5129 1674.79  5139.5 1674.85
  5146.4 1676.16  5159.5 1676.22  5165.6 1677.29  5179.5 1677.77  5185.2 1679.09
  5195.6 1679.57  5286.5 1686.56  5309.1  1689.6  5342.8 1691.39  5389.7 1696.46
#Mann= 9 ,-1 , 0
  4530.4     .07       0    4621    .035       0  4935.6     .07       0
  4938.9    .035       0  4996.8      .1       0  5006.6     .07       0
  5008.4     .05       0  5012.8     .07       0  5195.6      .1       0
Bank Sta=5008.4,5012.8
XS Rating Curve= 0 ,0
Exp/Cntr=0.3,0.1

Type RM Length L Ch R = 1 ,24479   ,448,448,448
BEGIN DESCRIPTION:
Elm Creek 49.0
END DESCRIPTION:
XS GIS Cut Line= 3
      1960974.98       13869025.        1961375.       13868975.
      1961774.98     13868575.02
#Sta/Elev= 30
  4596.9  1668.7  4602.9 1668.46  4732.6 1663.77  4921.6    1657  4951.9 1657.34
  4976.1 1655.32  4999.5 1656.22  5005.3  1655.7  5019.2 1651.72  5019.5 1651.22
  5023.8 1651.72  5026.1 1653.72  5038.5  1656.2  5054.7 1656.61    5077 1657.55
  5097.9  1657.3  5125.6 1659.51  5146.4 1660.33  5191.9 1664.05  5208.2 1665.75
  5225.9 1668.83  5297.3 1675.41  5373.7 1686.05  5416.8 1687.03  5425.3 1690.18
  5444.9  1693.6  5471.9 1697.24  5509.8 1700.72  5531.3 1705.17  5565.7 1709.26
#Mann= 9 ,-1 , 0
  4596.9     .07       0  4602.9    .035       0  4732.6     .07       0
  5019.2     .05       0  5023.8     .07       0  5054.7      .1       0
  5125.6    .035       0  5146.4      .1       0  5444.9     .07       0
Bank Sta=5019.2,5023.8
XS Rating Curve= 0 ,0
Exp/Cntr=0.3,0.1

Type RM Length L Ch R = 1 ,24031   ,474,474,474
BEGIN DESCRIPTION:
Elm Creek 48.0
END DESCRIPTION:
XS GIS Cut Line= 3
      1961324.96       13869225.        1961675.       13869225.
      1962074.98     13868825.02
#Sta/Elev= 30
  4645.2 1656.84  4680.4 1655.18  4881.4 1652.42  4966.5  1649.8  4999.8 1649.18
  5005.1 1647.17  5008.1 1642.21  5008.4 1641.71  5012.7 1642.21    5021 1642.24
  5027.3 1648.32  5029.5 1649.33  5121.7 1650.25  5185.8 1656.36  5242.6 1663.83
  5271.3 1668.91  5286.1 1672.71  5321.1 1684.45  5347.7 1687.01  5379.1 1693.21
    5388 1695.88  5402.8  1697.6  5421.9 1701.79  5436.8 1706.06  5464.3 1708.83
  5483.4 1713.36    5511 1716.95  5534.3 1724.79    5546 1726.11  5560.9 1729.94
#Mann= 6 ,-1 , 0
  4645.2      .1       0  4966.5     .07       0  5008.1     .05       0
  5012.7     .07       0  5185.8      .1       0  5379.1     .07       0
Bank Sta=5008.1,5012.7
XS Rating Curve= 0 ,0
Exp/Cntr=0.3,0.1

Type RM Length L Ch R = 1 ,23557   ,358,358,358
BEGIN DESCRIPTION:
Elm Creek 47.0
END DESCRIPTION:
XS GIS Cut Line= 3
      1961075.03       13869725.      1961951.08     13869612.25
      1962025.01     13869374.98
#Sta/Elev= 30
  4196.9 1671.31  4336.2 1660.04  4426.9 1655.31  4567.2 1650.91  4690.1 1648.32
  4756.6 1645.49    4796 1644.79  4835.3 1645.72  4866.2  1644.7  4941.2 1640.92
  4963.5 1641.17  4974.9 1640.34  4975.3 1639.84  4979.9 1640.34  5019.8 1643.27
  5028.9 1644.83    5044 1644.33  5091.6 1647.71    5101 1646.97  5129.7 1648.17
  5168.1 1647.67  5177.7 1648.21  5217.3 1655.28  5220.5 1656.79  5239.3 1661.12
    5255 1662.73  5262.1 1664.58  5273.9 1666.28  5287.8 1666.54  5328.7 1668.97
#Mann= 6 ,-1 , 0
  4196.9    .035       0  4567.2      .1       0  4866.2     .07       0
  4974.9     .05       0  4979.9     .07       0  5287.8      .1       0
Bank Sta=4974.9,4979.9
XS Rating Curve= 0 ,0
Exp/Cntr=0.3,0.1

Type RM Length L Ch R = 1 ,23199   ,553,553,553
BEGIN DESCRIPTION:
Elm Creek 46.0
END DESCRIPTION:
XS GIS Cut Line= 3
      1961424.99       13869975.      1961764.98     13869920.81
      1962268.64     13869540.98
#Sta/Elev= 30
  4697.1  1651.3    4716 1650.94  4738.6 1650.14  4816.3 1648.53  4871.5 1647.42
  4916.5 1644.16  4932.2 1640.22  4935.3 1639.01  4935.8 1637.84  4936.2 1637.34
  4940.8 1637.84  4947.4 1639.27  4978.4 1640.38  4992.9 1639.48  5017.3 1639.78
  5023.4 1638.96    5030 1639.21  5035.5 1638.67  5064.2  1640.3  5146.1 1640.56
  5169.4  1640.9    5192 1642.58    5259 1643.71    5422 1650.46  5445.3 1651.41
  5466.2 1653.99  5527.2 1654.19  5537.4 1655.16  5631.6 1658.31  5672.2 1664.66
#Mann= 10 ,-1 , 0
  4697.1     .07       0    4716    .035       0  4738.6     .07       0
  4816.3    .035       0  4916.5     .07       0  4935.8     .05       0
  4940.8     .07       0    5030      .1       0  5146.1     .07       0
    5422      .1       0
Bank Sta=4935.8,4940.8
XS Rating Curve= 0 ,0
Exp/Cntr=0.3,0.1

Type RM Length L Ch R = 1 ,22646   ,473,473,473
BEGIN DESCRIPTION:
Elm Creek 45.0
END DESCRIPTION:
XS GIS Cut Line= 3
      1962075.02     13870324.96        1962175.       13870125.
      1962575.03     13869724.97
#Sta/Elev= 30
  4776.3 1646.97    4808 1646.82    4824 1645.81  4854.2 1642.78  4887.7 1635.52
  4961.5 1633.38    4969 1631.85  4971.6 1629.73  4972.1 1629.23  4978.2 1629.73
  4978.3 1630.94  4980.8 1632.42    4985  1633.6  5027.4 1632.74  5057.4 1633.25
  5082.2 1634.61  5108.3 1637.25  5239.2 1643.61  5262.7 1645.57    5295 1647.56
  5303.5 1647.25  5318.6  1648.7  5363.9 1651.26  5400.7  1654.6    5418 1655.38
  5481.7 1663.12  5506.4 1665.11  5536.1 1669.82  5548.9 1673.25  5565.6 1676.03
#Mann= 6 ,-1 , 0
  4776.3     .07       0  4971.6     .05       0  4978.2     .07       0
  5262.7      .1       0  5318.6     .07       0  5363.9      .1       0
Bank Sta=4971.6,4978.2
XS Rating Curve= 0 ,0
Exp/Cntr=0.3,0.1

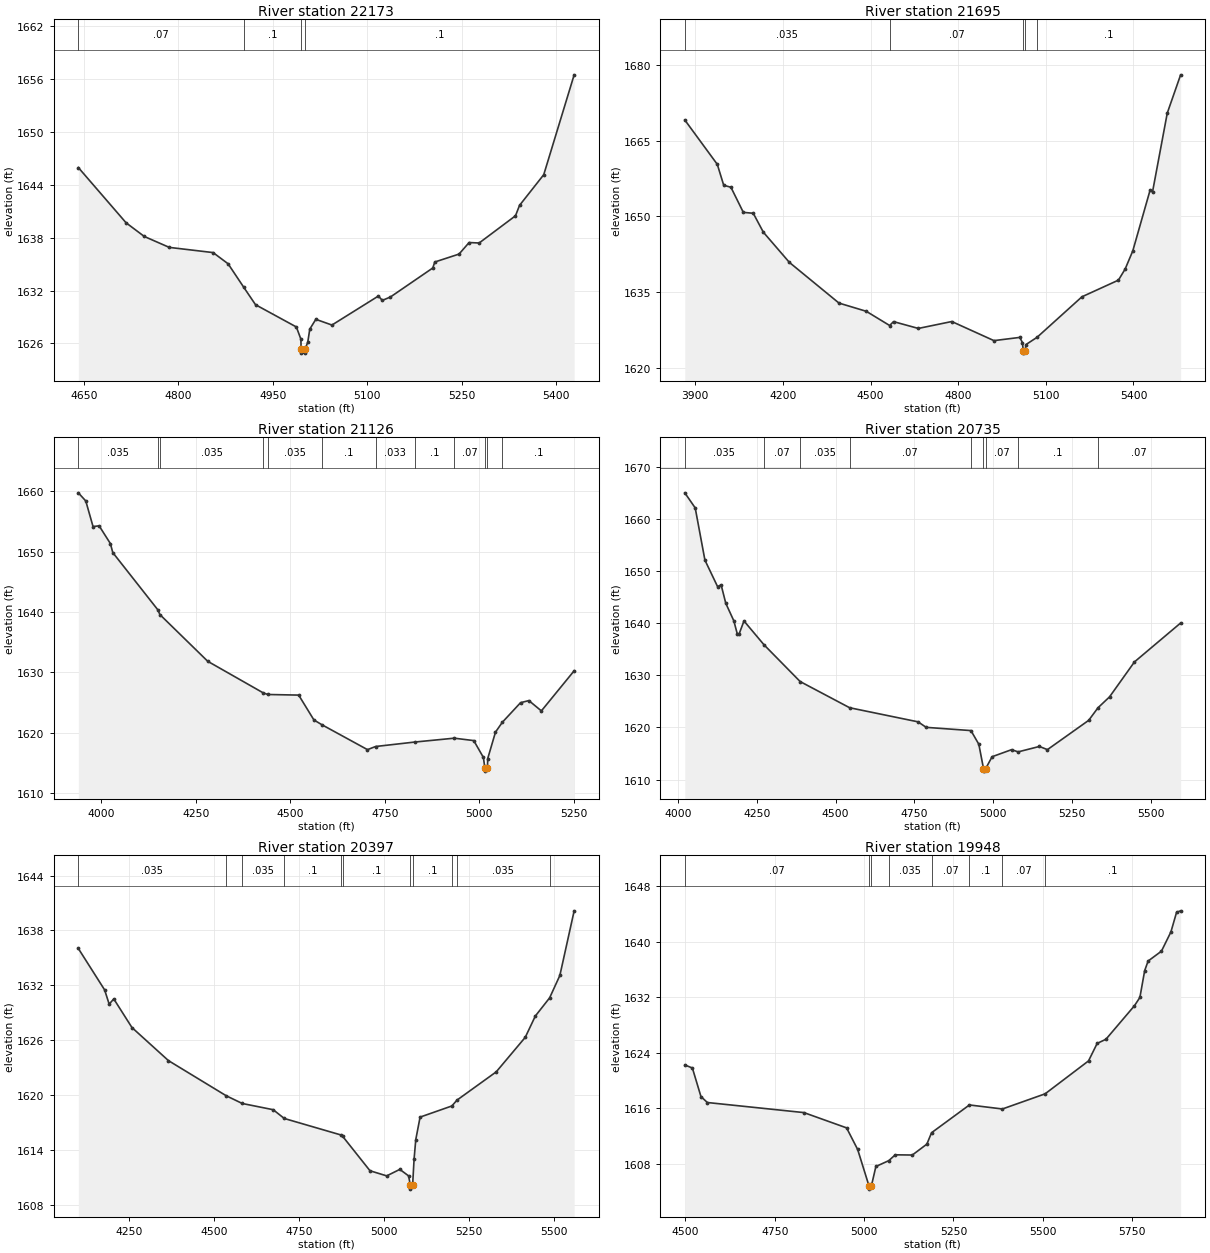
Type RM Length L Ch R = 1 ,22173   ,478,478,478
BEGIN DESCRIPTION:
Elm Creek 44.0
END DESCRIPTION:
XS GIS Cut Line= 3
      1962275.01     13870524.99        1962575.       13870325.
      1962724.98     13869925.04
#Sta/Elev= 30
  4640.9 1645.97  4716.8 1639.69  4745.7 1638.14  4785.4  1636.9    4855 1636.31
  4878.8 1635.04  4903.6 1632.38  4922.4 1630.39  4987.3 1627.86  4994.5 1626.47
  4994.8 1625.39  4995.3 1624.89  5000.9 1624.89  5001.4 1625.39  5005.4 1626.13
  5008.6 1627.62  5018.2 1628.73  5043.8 1628.08  5117.5 1631.37  5123.9 1630.88
  5136.8 1631.27    5204 1634.56  5207.2 1635.24  5245.7 1636.14  5261.7 1637.45
  5277.7  1637.4  5335.4 1640.49  5341.8 1641.67  5380.3 1645.16  5428.6  1656.5
#Mann= 4 ,-1 , 0
  4640.9     .07       0  4903.6      .1       0  4994.8     .05       0
  5001.4      .1       0
Bank Sta=4994.8,5001.4
XS Rating Curve= 0 ,0
Exp/Cntr=0.3,0.1

Type RM Length L Ch R = 1 ,21695   ,569,569,569
BEGIN DESCRIPTION:
Elm Creek 43.0
END DESCRIPTION:
XS GIS Cut Line= 3
      1962175.03     13871224.97        1962975.       13870425.
      1963374.99     13870025.01
#Sta/Elev= 30
  3864.3 1669.15  3975.5 1660.35  3997.5  1656.2  4022.2  1655.8  4064.6 1650.82
  4098.6 1650.64  4133.2 1646.88  4222.3 1640.89    4392 1632.82  4485.4 1631.19
  4565.4 1628.37  4578.7 1629.14  4663.6 1627.79  4778.1 1629.16  4922.4 1625.37
  5010.8 1626.01    5020 1624.97  5022.6 1623.39  5023.1 1622.89  5029.3 1623.39
    5032 1624.59  5070.2 1626.04  5223.6 1634.07  5348.4 1637.37  5371.4 1639.57
  5397.6 1643.18    5457 1655.27  5465.1 1654.86  5515.6 1670.52  5561.3 1678.11
#Mann= 5 ,-1 , 0
  3864.3    .035       0  4565.4     .07       0  5022.6     .05       0
  5029.3     .07       0  5070.2      .1       0
Bank Sta=5022.6,5029.3
XS Rating Curve= 0 ,0
Exp/Cntr=0.3,0.1

Type RM Length L Ch R = 1 ,21126   ,391,391,391
BEGIN DESCRIPTION:
Elm Creek 42.0
END DESCRIPTION:
XS GIS Cut Line= 3
      1962425.01     13871524.99      1963243.03      13870793.8
      1963374.97     13870625.03
#Sta/Elev= 30
  3939.5 1659.74  3959.2 1658.39  3978.4 1654.15  3994.5 1654.27  4024.3 1651.33
  4030.6 1649.84  4149.3 1640.39  4155.3 1639.56  4281.8 1631.82  4427.9 1626.61
  4440.5 1626.32  4522.3 1626.22  4562.6  1622.1  4583.1 1621.33  4704.3 1617.18
  4725.7  1617.7  4829.4 1618.44  4933.8 1619.08  4985.4 1618.68  5010.9 1615.88
  5014.7 1614.12  5015.2 1613.62  5021.6 1614.12  5022.2 1615.68  5042.8 1620.08
    5061 1621.72  5109.1 1624.96  5131.1 1625.31  5164.2  1623.6  5250.9 1630.25
#Mann= 12 ,-1 , 0
  3939.5    .035       0  4149.3     .07       0  4155.3    .035       0
  4427.9     .07       0  4440.5    .035       0  4583.1      .1       0
  4725.7    .033       0  4829.4      .1       0  4933.8     .07       0
  5014.7     .05       0  5021.6     .07       0    5061      .1       0
Bank Sta=5014.7,5021.6
XS Rating Curve= 0 ,0
Exp/Cntr=0.3,0.1

Type RM Length L Ch R = 1 ,20735   ,338,338,338
BEGIN DESCRIPTION:
Elm Creek 41.0
END DESCRIPTION:
XS GIS Cut Line= 3
      1962474.97     13871725.02      1963298.55     13871147.72
        1963675.       13870725.
#Sta/Elev= 30
    4022 1665.08    4055 1662.18  4085.8 1652.15    4126 1647.05  4137.1 1647.41
  4151.9 1643.86  4177.4 1640.49  4188.4 1637.97    4194 1637.94  4209.6 1640.46
    4273 1635.89  4387.7 1628.82  4544.5 1623.79  4761.4 1621.08  4787.3 1620.02
  4929.1  1619.4  4954.1 1616.77  4968.9 1612.11  4969.4 1611.61  4975.9 1612.11
  4996.2 1614.38  5057.8 1615.73  5078.8 1615.31  5146.1 1616.35  5171.6 1615.74
  5302.4 1621.37  5331.8 1623.78  5368.5 1625.88  5447.4 1632.59  5593.8 1640.07
#Mann= 9 ,-1 , 0
    4022    .035       0    4273     .07       0  4387.7    .035       0
  4544.5     .07       0  4929.1     .07       0  4968.9     .05       0
  4975.9     .07       0  5078.8      .1       0  5331.8     .07       0
Bank Sta=4968.9,4975.9
XS Rating Curve= 0 ,0
Exp/Cntr=0.3,0.1

Type RM Length L Ch R = 1 ,20397   ,449,449,449
BEGIN DESCRIPTION:
Elm Creek 40.0
END DESCRIPTION:
XS GIS Cut Line= 3
        1962725.       13871775.        1963525.       13871375.
      1963924.99     13870975.01
#Sta/Elev= 30
  4100.4 1636.02  4177.8 1631.49  4191.2 1629.93  4204.8  1630.5  4258.3 1627.37
  4365.8 1623.75  4536.2  1619.9  4583.2 1619.06  4674.2 1618.38  4706.9 1617.42
  4872.5 1615.63  4878.5 1615.48  4959.3  1611.7  5008.5 1611.14  5047.1 1611.85
  5072.9 1611.14  5077.8 1610.19  5078.3 1609.69  5084.9 1610.19  5089.1 1612.97
  5094.1 1615.11  5106.8 1617.57  5200.4 1618.79  5215.5 1619.43    5331 1622.52
  5416.5  1626.3  5446.2 1628.63  5488.3 1630.62  5518.4 1633.07  5560.5 1640.14
#Mann= 11 ,-1 , 0
  4100.4    .035       0  4536.2     .07       0  4583.2    .035       0
  4706.9      .1       0  4872.5     .07       0  4878.5      .1       0
  5077.8     .05       0  5084.9      .1       0  5200.4     .07       0
  5215.5    .035       0  5488.3     .07       0
Bank Sta=5077.8,5084.9
XS Rating Curve= 0 ,0
Exp/Cntr=0.3,0.1

Type RM Length L Ch R = 1 ,19948   ,299,299,299
BEGIN DESCRIPTION:
Elm Creek 39.0
END DESCRIPTION:
XS GIS Cut Line= 3
      1963174.99       13871775.      1963651.86      13871763.1
      1964508.88     13871455.14
#Sta/Elev= 30
  4498.1 1622.23  4519.3 1621.79  4543.3 1617.68  4561.2 1616.82  4831.4 1615.37
  4950.9 1613.17  4981.9 1610.06  5013.4 1604.85  5013.9 1604.35  5020.5 1604.85
  5032.9 1607.61    5069 1608.45  5087.1 1609.29  5134.9 1609.26  5175.6 1610.83
  5188.7 1612.47  5294.7 1616.47    5387 1615.89  5506.5 1618.07    5628 1622.81
  5652.2 1625.33  5676.8 1625.93  5756.5 1630.75  5771.8 1631.95  5785.2 1635.81
  5794.8 1637.19  5832.1 1638.61  5858.6 1641.38  5874.4  1644.2  5885.8 1644.42
#Mann= 8 ,-1 , 0
  4498.1     .07       0  5013.4     .05       0  5020.5     .07       0
    5069    .035       0  5188.7     .07       0  5294.7      .1       0
    5387     .07       0  5506.5      .1       0
Bank Sta=5013.4,5020.5
XS Rating Curve= 0 ,0
Exp/Cntr=0.3,0.1