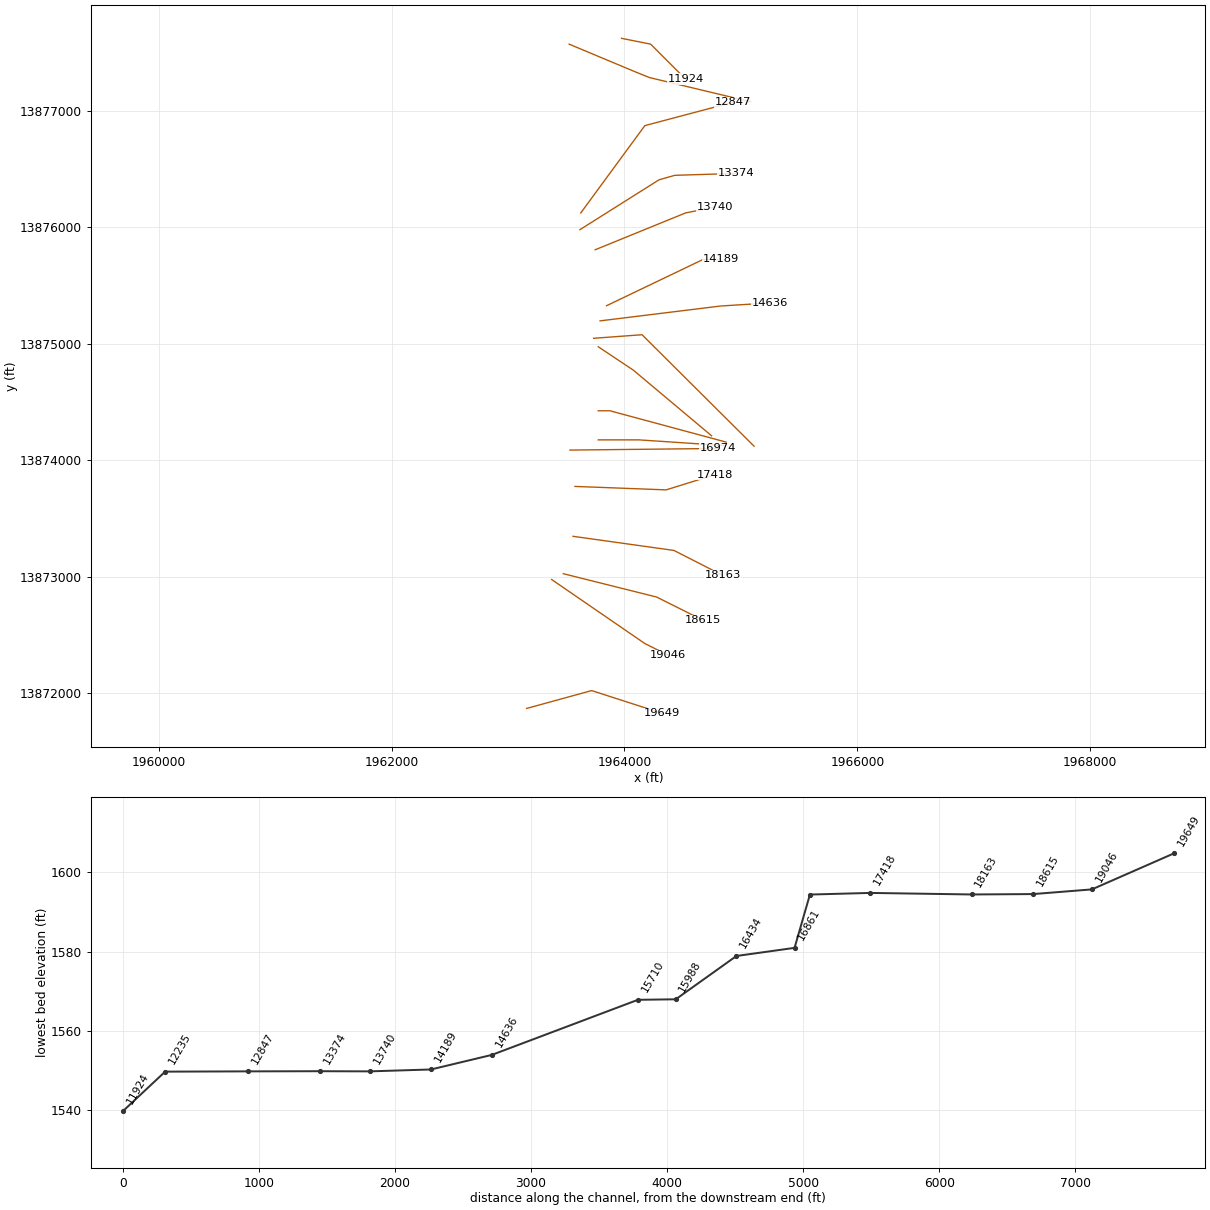
HEC-RAS study Elm Creek.prj: Elm Creek Base Level Engineering

--- Elm Creek.g01 (geometry) --- (continued)

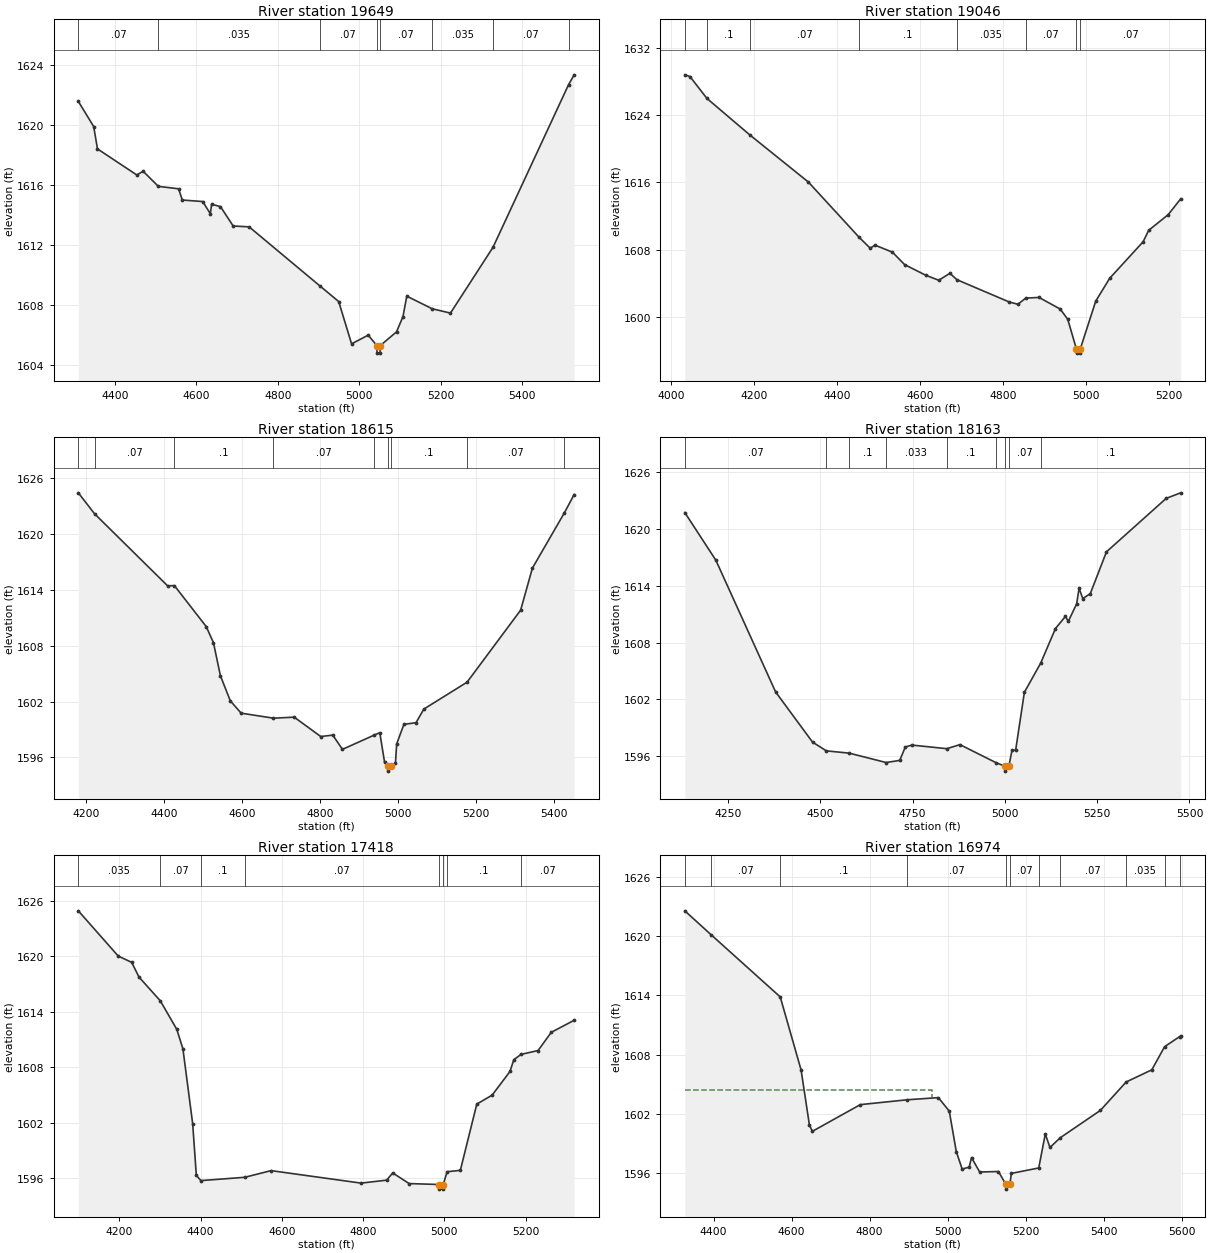
Type RM Length L Ch R = 1 ,19649   ,603,603,603
BEGIN DESCRIPTION:
Elm Creek 38.0
END DESCRIPTION:
XS GIS Cut Line= 3
      1963159.87     13871867.36      1963718.24     13872020.86
      1964325.03     13871824.99
#Sta/Elev= 30
  4310.3  1621.6    4348 1619.92  4357.3 1618.43  4453.9 1616.69  4469.3 1616.94
  4506.7 1615.93  4556.4 1615.77  4565.4 1615.02  4615.5 1614.92  4634.2 1614.11
  4637.3 1614.74  4659.1 1614.58  4690.2 1613.29  4729.5 1613.23  4902.3 1609.31
  4949.2 1608.25  4980.8 1605.43  5021.7 1606.01  5042.8 1605.31  5043.3 1604.81
  5050.6 1604.81  5051.1 1605.31  5091.1 1606.23  5106.9 1607.24  5116.3 1608.61
  5178.5 1607.77  5223.5 1607.48  5327.9 1611.87  5513.4 1622.72    5527 1623.37
#Mann= 8 ,-1 , 0
  4310.3     .07       0  4506.7    .035       0  4902.3     .07       0
  5042.8     .05       0  5051.1     .07       0  5178.5    .035       0
  5327.9     .07       0  5513.4    .035       0
Bank Sta=5042.8,5051.1
XS Rating Curve= 0 ,0
Exp/Cntr=0.3,0.1

Type RM Length L Ch R = 1 ,19046   ,431,431,431
BEGIN DESCRIPTION:
Elm Creek 37.0
END DESCRIPTION:
XS GIS Cut Line= 3
      1963375.01     13872974.99        1964175.       13872425.
      1964374.98     13872325.01
#Sta/Elev= 30
  4032.9 1628.79  4045.3 1628.59  4086.3 1625.98  4190.2 1621.62  4330.5 1616.05
    4453 1609.47  4479.4 1608.19  4491.3 1608.54  4533.1 1607.71  4562.2 1606.24
  4613.2 1604.97  4644.8 1604.37  4671.4  1605.2  4688.3 1604.44  4814.3 1601.79
  4835.3 1601.52  4854.3 1602.25  4886.2 1602.33  4937.2 1600.95  4955.4 1599.73
  4976.2 1596.21  4976.7 1595.71  4985.1 1595.71  4985.6 1596.21  5022.9  1601.9
  5056.5 1604.61    5137 1608.95  5150.4 1610.31  5197.4 1612.17  5227.3 1614.04
#Mann= 8 ,-1 , 0
  4032.9    .035       0  4086.3      .1       0  4190.2     .07       0
    4453      .1       0  4688.3    .035       0  4854.3     .07       0
  4976.2     .05       0  4985.6     .07       0
Bank Sta=4976.2,4985.6
XS Rating Curve= 0 ,0
Exp/Cntr=0.3,0.1

Type RM Length L Ch R = 1 ,18615   ,452,452,452
BEGIN DESCRIPTION:
Elm Creek 36.0
END DESCRIPTION:
XS GIS Cut Line= 3
      1963474.95     13873025.01        1964275.       13872825.
      1964675.02     13872624.99
#Sta/Elev= 30
  4179.6 1624.44  4221.2 1622.19  4408.7 1614.44    4426 1614.47  4507.6 1610.07
  4526.2 1608.34    4544 1604.79  4569.5 1602.08  4597.3 1600.76  4680.2 1600.22
  4733.4 1600.33  4801.4 1598.25  4832.3  1598.4  4857.1 1596.87    4938 1598.39
  4952.9 1598.66  4965.3 1595.46  4972.9 1595.03  4973.4 1594.53  4982.4 1595.03
  4993.1 1595.39  4996.2 1597.46  5014.8 1599.55  5045.9 1599.74    5066  1601.2
  5176.8 1604.09  5314.2 1611.83  5344.4 1616.35  5426.4 1622.29  5451.5 1624.26
#Mann= 9 ,-1 , 0
  4179.6      .1       0  4221.2     .07       0    4426      .1       0
  4680.2     .07       0    4938      .1       0  4972.9     .05       0
  4982.4      .1       0  5176.8     .07       0  5426.4      .1       0
Bank Sta=4972.9,4982.4
XS Rating Curve= 0 ,0
Exp/Cntr=0.3,0.1

Type RM Length L Ch R = 1 ,18163   ,745,745,745
BEGIN DESCRIPTION:
Elm Creek 35.0
END DESCRIPTION:
XS GIS Cut Line= 3
      1963558.51      13873346.3        1964425.       13873225.
      1964842.11     13873011.76
#Sta/Elev= 30
  4132.6 1621.74  4216.8  1616.7  4378.7 1602.79  4478.6  1597.5  4516.2 1596.57
  4577.9 1596.33  4677.9 1595.34  4714.9 1595.56  4730.1 1596.98  4748.2 1597.18
  4842.5  1596.8  4878.1 1597.23  4974.9 1595.34  5000.9 1594.93  5001.4 1594.43
  5010.6 1594.93    5019 1596.61  5029.1 1596.66  5052.7 1602.76  5096.9 1605.84
  5136.9 1609.49  5163.9 1610.77  5171.6 1610.24  5194.2 1612.09  5200.9 1613.74
    5211 1612.65  5231.3 1613.18  5275.1 1617.59  5436.8 1623.23    5476 1623.82
#Mann= 9 ,-1 , 0
  4132.6     .07       0  4516.2    .035       0  4577.9      .1       0
  4677.9    .033       0  4842.5      .1       0  4974.9     .07       0
  5000.9     .05       0  5010.6     .07       0  5096.9      .1       0
Bank Sta=5000.9,5010.6
XS Rating Curve= 0 ,0
Exp/Cntr=0.3,0.1

Type RM Length L Ch R = 1 ,17418   ,444,444,444
BEGIN DESCRIPTION:
Elm Creek 34.0
END DESCRIPTION:
XS GIS Cut Line= 3
      1963575.03       13873775.      1964357.51     13873745.38
      1964775.01       13873875.
#Sta/Elev= 30
  4099.1  1624.9  4197.3 1620.01  4230.4 1619.33  4248.4 1617.74  4300.9 1615.17
  4341.4 1612.09  4356.5 1609.98  4380.5 1601.88  4389.5 1596.31  4400.8 1595.74
  4508.8  1596.1  4573.4 1596.82  4794.8 1595.47  4857.8 1595.79  4872.8 1596.57
  4913.2 1595.42  4986.5 1595.32    4987 1594.82  4996.6 1594.82  4997.1 1595.32
  5006.7  1596.7  5039.2 1596.85  5079.7 1604.01  5117.4 1604.98  5161.4 1607.54
  5170.8 1608.81  5188.5 1609.38  5230.5  1609.8    5263 1611.77  5319.3 1613.07
#Mann= 8 ,-1 , 0
  4099.1    .035       0  4300.9     .07       0  4400.8      .1       0
  4508.8     .07       0  4986.5     .05       0  4997.1     .07       0
  5006.7      .1       0  5188.5     .07       0
Bank Sta=4986.5,4997.1
XS Rating Curve= 0 ,0
Exp/Cntr=0.3,0.1

Type RM Length L Ch R = 1 ,16974   ,113,113,113
BEGIN DESCRIPTION:
Mapping XS e30e0f54
END DESCRIPTION:
XS GIS Cut Line= 2
       1963532.3     13874087.23      1964803.12     13874101.12
#Sta/Elev= 30
  4326.4 1622.54  4394.5  1620.1    4571 1613.84  4624.5 1606.45  4645.7 1600.92
  4653.3 1600.25  4776.2 1602.95    4896 1603.44  4976.4 1603.66  5004.3 1602.29
  5022.3  1598.2  5037.3 1596.44  5055.3 1596.63  5061.3  1597.6  5082.3 1596.14
  5130.4 1596.19    5149 1594.91  5149.5 1594.41  5159.7 1594.91  5163.4    1596
  5233.6 1596.55  5250.4 1599.98  5262.4 1598.62  5288.6  1599.6  5391.4 1602.36
  5457.7 1605.24  5523.4 1606.47  5556.3 1608.81  5594.5 1609.82  5597.3 1609.89
#Mann= 11 ,-1 , 0
  4326.4    .035       0  4394.5     .07       0    4571      .1       0
    4896     .07       0    5149     .05       0  5159.7     .07       0
  5233.6      .1       0  5288.6     .07       0  5457.7    .035       0
  5556.3     .07       0  5594.5    .035       0
#XS Ineff= 2 , 0
         4960.84 1604.39
Permanent Ineff=
       F       F
Bank Sta=5149,5159.7
XS Rating Curve= 0 ,0
Exp/Cntr=0.3,0.1

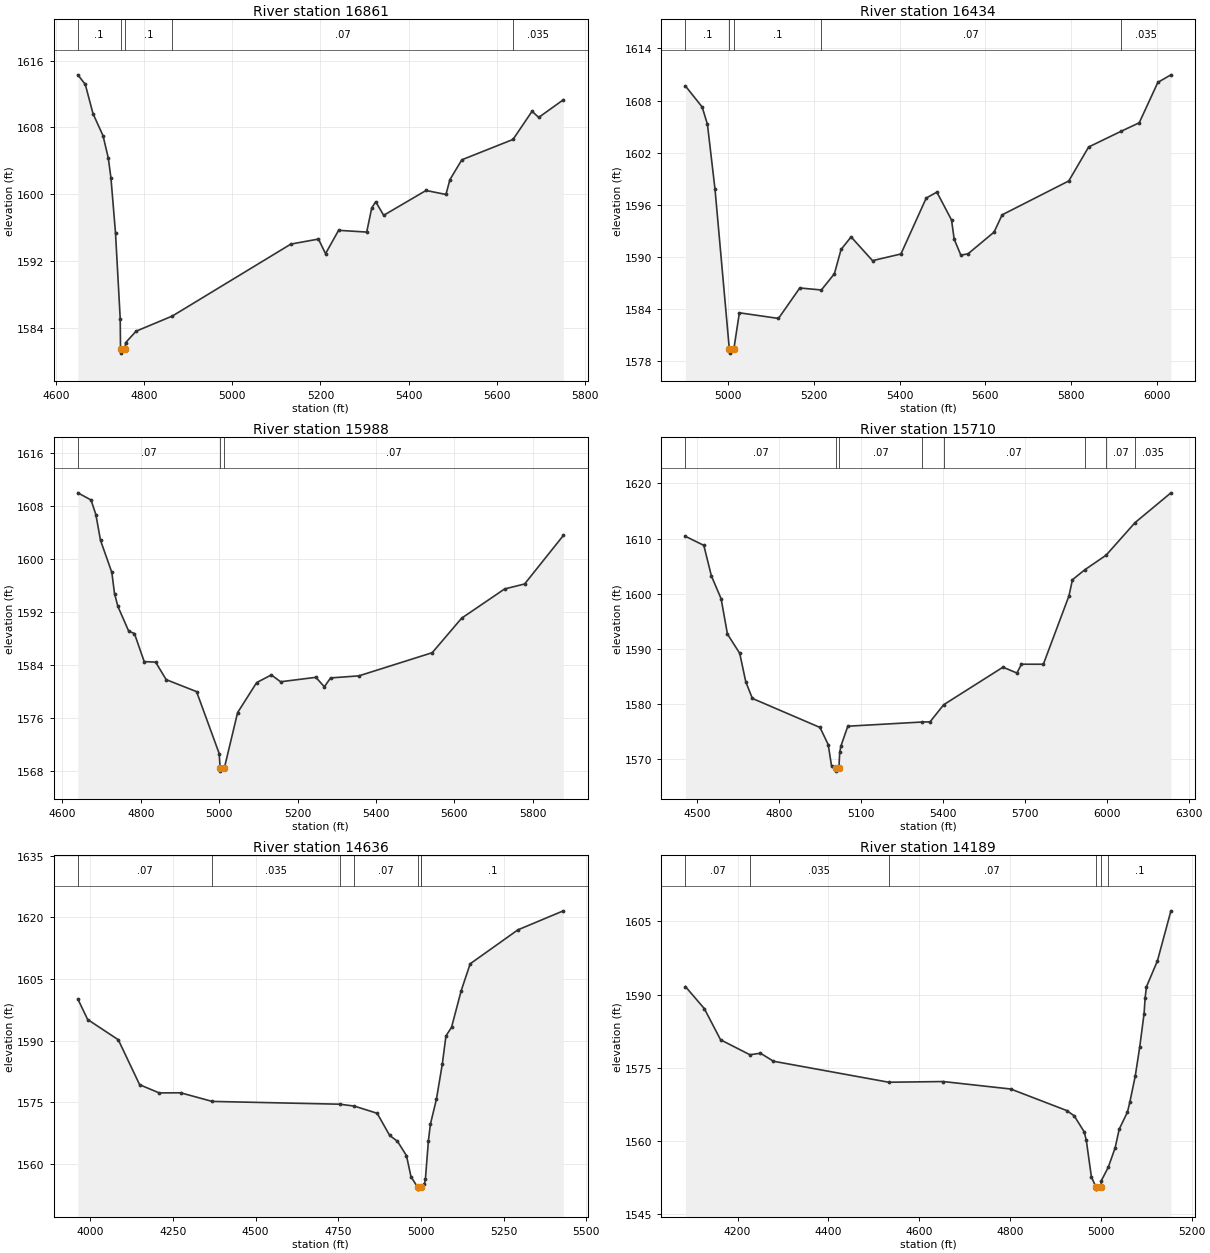
Type RM Length L Ch R = 1 ,16861   ,427,427,427
BEGIN DESCRIPTION:
Elm Creek 33.0
END DESCRIPTION:
XS GIS Cut Line= 3
      1963774.99       13874175.        1964125.       13874175.
      1964875.02       13874125.
#Sta/Elev= 30
  4649.6 1614.31  4666.5 1613.17  4684.1 1609.65  4706.8 1607.01  4718.8 1604.32
  4724.8 1601.92  4735.1 1595.36  4745.8 1585.07  4746.5 1581.43    4747 1580.93
  4757.2 1581.43  4757.8 1582.17  4781.8 1583.56  4864.1 1585.38  5133.1 1594.01
  5195.6 1594.61  5211.7 1592.86  5241.3 1595.66  5305.1 1595.45  5316.5 1598.34
  5325.5 1599.09  5343.6 1597.46  5439.8 1600.44  5484.9 1599.96  5493.9 1601.74
    5521 1604.12  5637.1 1606.56  5680.3 1609.94  5695.4  1609.2  5751.3 1611.32
#Mann= 5 ,-1 , 0
  4649.6      .1       0  4746.5     .05       0  4757.2      .1       0
  4864.1     .07       0  5637.1    .035       0
Bank Sta=4746.5,4757.2
XS Rating Curve= 0 ,0
Exp/Cntr=0.3,0.1

Type RM Length L Ch R = 1 ,16434   ,446,446,446
BEGIN DESCRIPTION:
Elm Creek 32.0
END DESCRIPTION:
XS GIS Cut Line= 3
      1963774.99       13874425.        1963875.       13874425.
      1964872.65     13874155.94
#Sta/Elev= 30
  4900.1 1609.68  4939.3 1607.25  4951.6 1605.24  4969.3 1597.75  5002.6 1579.38
  5003.1 1578.88  5013.3 1579.38  5026.1 1583.53  5117.4 1582.88  5167.1 1586.39
  5217.5 1586.16  5247.9 1588.03  5263.5 1590.83  5286.9 1592.28  5336.9 1589.54
  5403.2 1590.31  5462.3 1596.76  5487.1 1597.44  5521.3 1594.23  5527.5 1592.02
    5543 1590.18  5559.6 1590.32  5620.6 1592.83  5639.4 1594.82    5795 1598.73
  5841.3 1602.64  5916.1 1604.43  5959.4 1605.43  6002.9 1610.09  6033.4 1610.96
#Mann= 5 ,-1 , 0
  4900.1      .1       0  5002.6     .05       0  5013.3      .1       0
  5217.5     .07       0  5916.1    .035       0
Bank Sta=5002.6,5013.3
XS Rating Curve= 0 ,0
Exp/Cntr=0.3,0.1

Type RM Length L Ch R = 1 ,15988   ,278,278,278
BEGIN DESCRIPTION:
Elm Creek 31.0
END DESCRIPTION:
XS GIS Cut Line= 3
        1963775.       13874975.        1964075.       13874775.
      1964747.98      13874210.1
#Sta/Elev= 30
  4639.2 1609.97  4672.9 1608.89  4685.3 1606.68  4697.1  1602.8    4726 1597.95
  4732.9 1594.75  4741.5 1592.81  4769.2 1589.06  4783.7 1588.72  4808.6 1584.48
  4837.8 1584.39  4864.8 1581.75  4942.3 1579.94    5000 1570.59  5002.4 1568.43
  5002.9 1567.93  5013.3 1568.43    5047 1576.77  5095.7 1581.31  5133.2 1582.46
  5156.7 1581.43  5246.8  1582.1  5268.4 1580.67  5284.3 1582.01  5356.5 1582.32
  5543.7 1585.82  5618.9 1591.04  5728.5 1595.45  5779.5  1596.2  5878.4 1603.53
#Mann= 3 ,-1 , 0
  4639.2     .07       0  5002.4     .05       0  5013.3     .07       0
#XS Ineff= 2 , 0
         4837.24 1584.39
Permanent Ineff=
       F       F
Bank Sta=5002.4,5013.3
XS Rating Curve= 0 ,0
Exp/Cntr=0.3,0.1

Type RM Length L Ch R = 1 ,15710   ,1074,1074,1074
BEGIN DESCRIPTION:
Elm Creek 30.0
END DESCRIPTION:
XS GIS Cut Line= 3
      1963734.99     13875047.82      1964150.92     13875078.41
      1965113.33     13874120.25
#Sta/Elev= 30
  4457.5  1610.4  4524.9 1608.76  4552.5 1603.23  4588.1 1599.08  4611.3 1592.66
  4656.2 1589.17  4678.3    1584  4702.4 1580.99  4949.7 1575.72  4979.6 1572.62
  4992.1 1568.67  5007.8  1568.3  5008.3  1567.8  5018.7  1568.3  5021.7 1571.23
  5026.3 1572.38  5051.3 1575.95  5322.9 1576.71  5351.9 1576.74  5401.9 1579.85
  5618.6 1586.66  5669.4  1585.6  5686.3  1587.2  5766.2 1587.19  5859.9  1599.6
  5872.5 1602.52  5917.2 1604.31  5995.5 1606.97  6101.6 1612.89  6232.6 1618.29
#Mann= 8 ,-1 , 0
  4457.5     .07       0  5007.8     .05       0  5018.7     .07       0
  5322.9      .1       0  5401.9     .07       0  5917.2      .1       0
  5995.5     .07       0  6101.6    .035       0
Bank Sta=5007.8,5018.7
XS Rating Curve= 0 ,0
Exp/Cntr=0.3,0.1

Type RM Length L Ch R = 1 ,14636   ,447,447,447
BEGIN DESCRIPTION:
Elm Creek 29.0
END DESCRIPTION:
XS GIS Cut Line= 3
      1963790.64     13875197.45        1964825.       13875325.
      1965250.46     13875351.77
#Sta/Elev= 30
  3962.1 1600.16  3991.9 1595.15  4084.5 1590.23  4149.1 1579.28  4208.2 1577.29
    4273 1577.32  4368.6 1575.22  4754.7 1574.54  4798.4 1574.08  4867.5 1572.33
  4905.2 1566.95  4928.9 1565.51  4956.1 1562.03  4969.8 1556.89  4989.7 1554.37
  4990.2 1553.87  5001.1 1554.37  5001.2 1554.43  5010.4 1555.01  5013.5 1556.45
  5022.5 1565.68  5028.5 1569.68  5046.6 1575.71  5064.6 1584.36  5075.5 1591.16
  5092.4 1593.26  5121.7 1602.19  5148.8 1608.72  5293.1 1616.98  5430.6 1621.61
#Mann= 7 ,-1 , 0
  3962.1     .07       0  4368.6    .035       0  4754.7     .07       0
  4798.4     .07       0  4989.7     .05       0  5001.1     .07       0
  5001.2      .1       0
Bank Sta=4989.7,5001.1
XS Rating Curve= 0 ,0
Exp/Cntr=0.3,0.1

Type RM Length L Ch R = 1 ,14189   ,449,449,449
BEGIN DESCRIPTION:
Elm Creek 28.0
END DESCRIPTION:
XS GIS Cut Line= 3
      1963846.32     13875327.72        1964675.       13875725.
      1964825.01       13875725.
#Sta/Elev= 30
  4085.2 1591.68  4126.8 1587.17  4162.7 1580.77  4227.2 1577.71  4250.5 1578.02
  4279.1 1576.38  4532.9 1572.08    4653 1572.22  4801.5 1570.69  4924.6 1566.29
  4941.2 1565.21  4963.3 1561.92  4967.9 1560.18  4979.1  1552.7  4988.7 1550.69
  4989.2 1550.19  5000.1 1550.69  5001.1 1551.93  5016.4 1554.71  5031.4 1558.65
  5040.4 1562.48  5058.4 1565.95  5063.7 1567.98  5075.7 1573.36  5085.4 1579.22
  5095.1 1586.14  5097.4 1589.37  5100.4 1591.65  5124.4 1596.91  5154.2 1607.18
#Mann= 6 ,-1 , 0
  4085.2     .07       0  4227.2    .035       0  4532.9     .07       0
  4988.7     .05       0  5000.1     .07       0  5016.4      .1       0
Bank Sta=4988.7,5000.1
XS Rating Curve= 0 ,0
Exp/Cntr=0.3,0.1

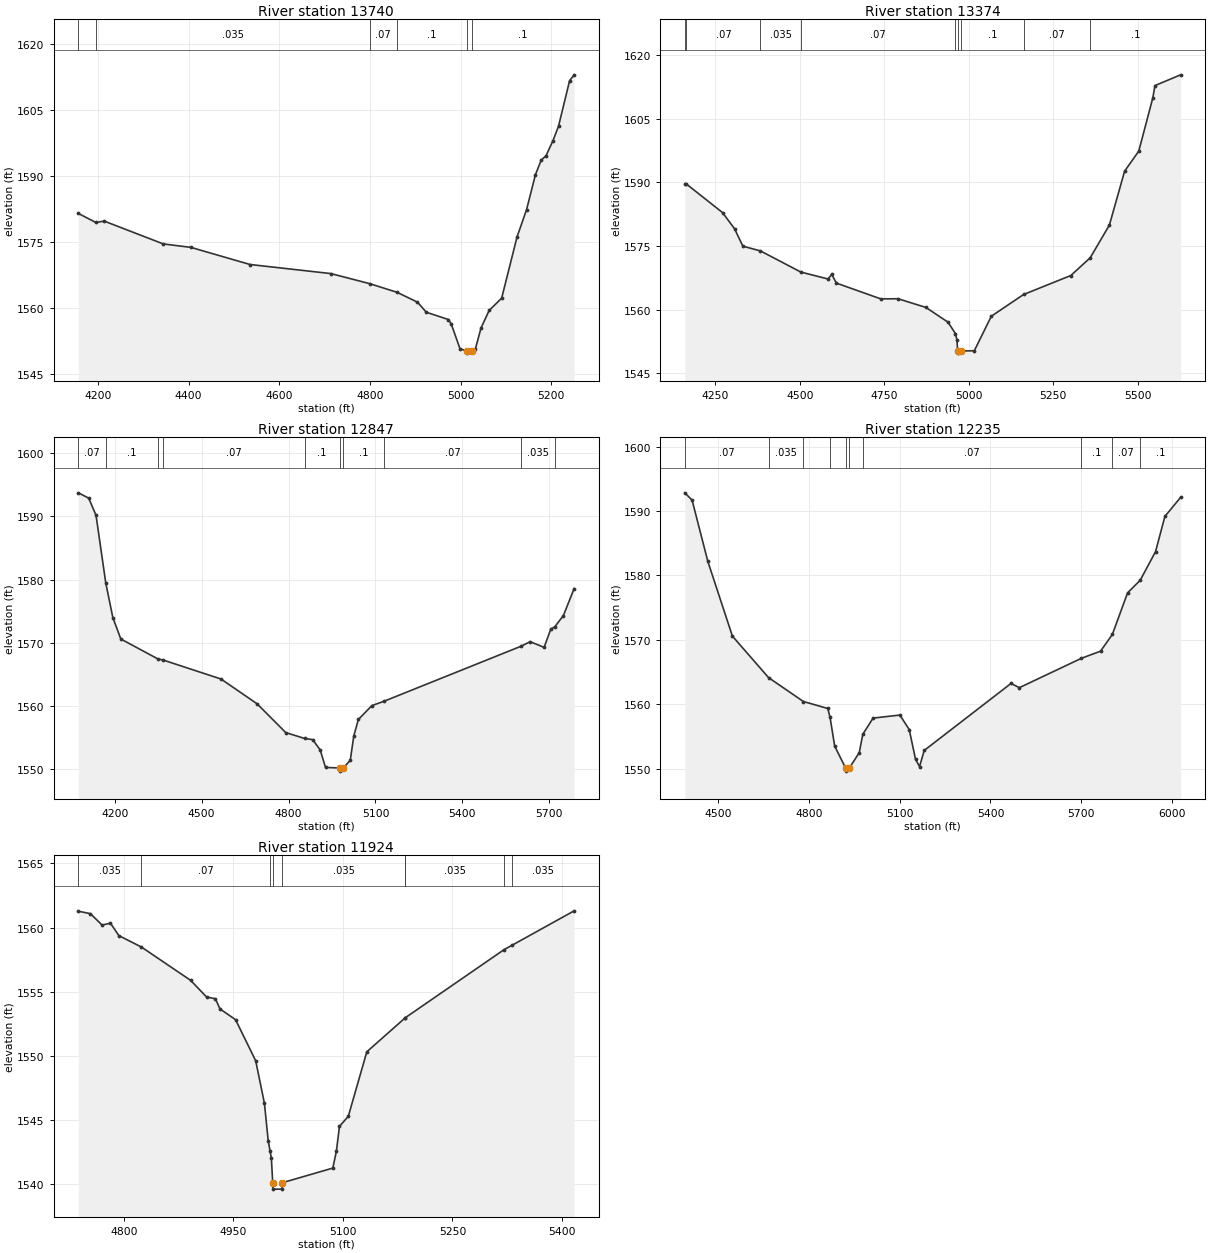
Type RM Length L Ch R = 1 ,13740   ,366,366,366
BEGIN DESCRIPTION:
Elm Creek 27.0
END DESCRIPTION:
XS GIS Cut Line= 3
      1963748.68     13875808.34        1964525.       13876125.
      1964775.03     13876175.01
#Sta/Elev= 30
  4156.9 1581.43  4195.4 1579.37    4214 1579.68  4344.3  1574.5    4405 1573.72
  4535.5 1569.83  4713.7 1567.77  4799.1 1565.49  4859.7 1563.52  4904.8 1561.28
  4924.3 1558.99  4972.9 1557.34  4979.3 1556.31  4998.6 1550.69  5014.2 1550.21
  5014.7 1549.71  5025.7 1550.21  5032.2 1550.55    5045 1555.45  5062.8 1559.39
  5090.4 1562.18  5124.4  1576.1  5145.4  1582.3  5164.9 1590.21  5177.6 1593.52
  5188.3 1594.53  5203.6 1597.95  5215.8 1601.22  5240.3 1611.58  5250.3 1612.89
#Mann= 6 ,-1 , 0
  4156.9     .07       0  4195.4    .035       0  4799.1     .07       0
  4859.7      .1       0  5014.2     .05       0  5025.7      .1       0
Bank Sta=5014.2,5025.7
XS Rating Curve= 0 ,0
Exp/Cntr=0.3,0.1

Type RM Length L Ch R = 1 ,13374   ,527,527,527
BEGIN DESCRIPTION:
Elm Creek 26.0
END DESCRIPTION:
XS GIS Cut Line= 4
      1963617.89      13875981.1      1964296.95     13876409.56
      1964432.78     13876448.05      1964954.82     13876464.22
#Sta/Elev= 30
  4160.2 1589.62  4164.9 1589.61  4271.7 1582.88  4307.2 1579.08    4332 1574.95
  4383.9 1573.84  4503.6 1568.85  4583.9 1567.22  4594.5 1568.32  4608.7 1566.25
  4739.9 1562.53  4790.6 1562.57  4873.2 1560.52  4938.6 1557.05  4960.6 1554.35
  4965.3  1552.8    4967 1550.25  4967.5 1549.75  4978.5 1550.25  5016.4 1550.31
  5066.8 1558.45  5162.2 1563.57  5301.8 1568.04  5359.2 1572.22  5415.9 1579.93
  5460.9 1592.62  5502.9 1597.37  5544.3  1609.9  5550.9 1612.81  5626.6 1615.34
#Mann= 9 ,-1 , 0
  4160.2      .1       0  4164.9     .07       0  4383.9    .035       0
  4503.6     .07       0  4960.6      .1       0    4967     .05       0
  4978.5      .1       0  5162.2     .07       0  5359.2      .1       0
Bank Sta=4967,4978.5
XS Rating Curve= 0 ,0
Exp/Cntr=0.3,0.1

Type RM Length L Ch R = 1 ,12847   ,612,612,612
BEGIN DESCRIPTION:
Elm Creek 25.0
END DESCRIPTION:
XS GIS Cut Line= 3
      1963625.01     13876125.01        1964175.       13876875.
      1964930.18      13877075.2
#Sta/Elev= 30
  4074.5 1593.74  4110.3  1592.9  4135.6 1590.18  4169.2 1579.48  4193.6    1574
  4221.2 1570.61  4349.2 1567.46  4368.4 1567.27  4567.1 1564.28  4691.5 1560.36
  4790.3 1555.81  4855.3 1554.88  4883.4 1554.69  4909.4 1553.05  4927.6 1550.29
    4977 1550.21  4977.5 1549.71  4988.7 1550.21    5013 1551.41  5025.4 1555.31
    5041 1557.88  5087.5 1560.07  5130.9 1560.79  5603.1 1569.48  5633.7 1570.19
  5682.1 1569.29  5705.1 1572.16    5719 1572.55  5748.6 1574.32  5785.8  1578.6
#Mann= 10 ,-1 , 0
  4074.5     .07       0  4169.2      .1       0  4349.2    .035       0
  4368.4     .07       0  4855.3      .1       0    4977     .05       0
  4988.7      .1       0  5130.9     .07       0  5603.1    .035       0
    5719     .07       0
Bank Sta=4977,4988.7
XS Rating Curve= 0 ,0
Exp/Cntr=0.3,0.1

Type RM Length L Ch R = 1 ,12235   ,311,311,311
BEGIN DESCRIPTION:
Elm Creek 24.0
END DESCRIPTION:
XS GIS Cut Line= 4
        1963525.       13877575.      1964091.46     13877337.69
      1964213.86     13877288.21      1965082.77     13877079.98
#Sta/Elev= 30
  4389.2 1592.82  4413.3 1591.69  4465.3 1582.19  4546.6 1570.59  4666.2 1564.15
  4781.4 1560.44  4862.1 1559.36  4869.6 1557.98  4884.9 1553.52  4920.7 1550.14
  4921.2 1549.64  4933.7 1550.14  4966.2 1552.52  4977.9 1555.36  5011.9 1557.87
  5100.4 1558.34  5131.4 1556.09  5152.3 1551.46  5165.6 1550.35    5181 1552.85
  5467.9 1563.24  5495.6 1562.59    5701 1567.15    5764 1568.25  5803.1 1570.84
  5853.5  1577.3  5895.3 1579.26    5946  1583.7  5976.9 1589.16  6028.9 1592.12
#Mann= 10 ,-1 , 0
  4389.2     .07       0  4666.2    .035       0  4781.4     .07       0
  4869.6    .035       0  4920.7     .05       0  4933.7    .035       0
  4977.9     .07       0    5701      .1       0  5803.1     .07       0
  5895.3      .1       0
Bank Sta=4920.7,4933.7
XS Rating Curve= 0 ,0
Exp/Cntr=0.3,0.1

Type RM Length L Ch R = 1 ,11924   ,486,486,486
BEGIN DESCRIPTION:
Elm Creek 23.0
END DESCRIPTION:
XS GIS Cut Line= 3
        1963975.       13877625.        1964225.       13877575.
      1964524.99     13877275.01
#Sta/Elev= 30
  4737.5 1561.28    4754 1561.09  4770.1  1560.2  4781.5 1560.35    4793 1559.38
  4823.9 1558.49  4891.2  1555.9  4913.1  1554.6  4925.3 1554.46  4931.5 1553.67
  4952.9 1552.83  4980.5 1549.62  4992.4 1546.32  4997.6  1543.4  5000.2 1542.58
  5001.9 1542.05  5003.8 1540.13  5004.3 1539.63  5016.5 1539.63    5017 1540.13
  5086.1 1541.27    5091 1542.58  5095.2 1544.52  5107.3  1545.3  5132.7 1550.33
  5184.4 1552.93  5185.6 1552.99  5320.5 1558.28  5331.7 1558.63  5416.7 1561.31
#Mann= 9 ,-1 , 0
  4737.5    .035       0  4823.9     .07       0  5000.2    .035       0
  5003.8     .05       0    5017    .035       0  5184.4     .07       0
  5185.6    .035       0  5320.5     .07       0  5331.7    .035       0
Bank Sta=5003.8,5017
XS Rating Curve= 0 ,0
Exp/Cntr=0.3,0.1