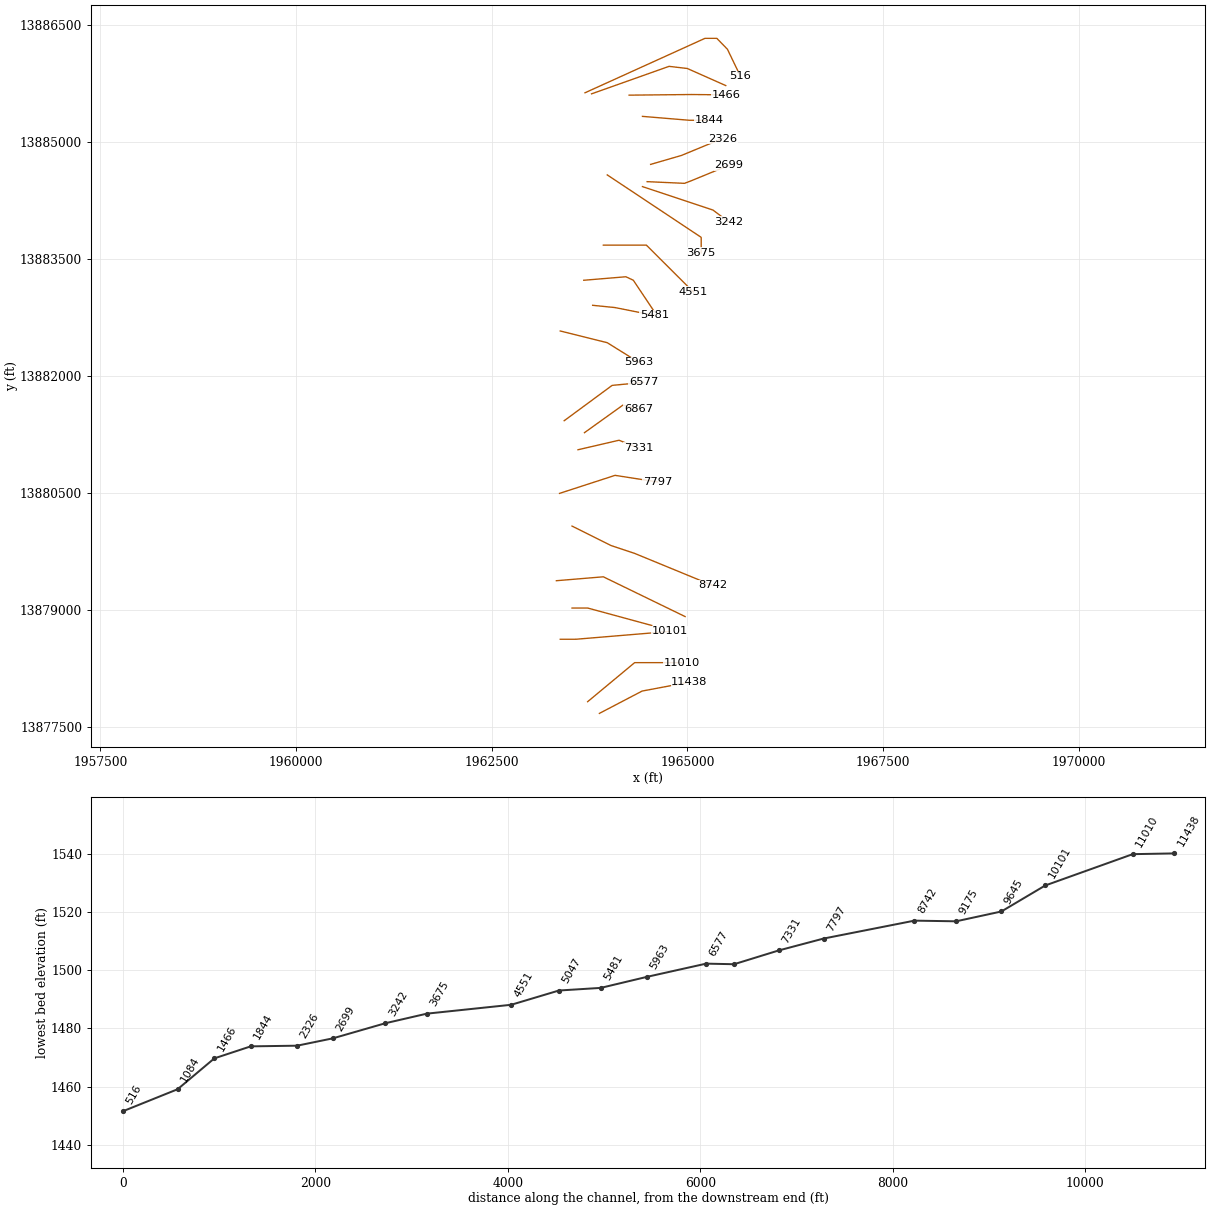
HEC-RAS study Elm Creek.prj: Elm Creek Base Level Engineering

--- Elm Creek.g01 (geometry) --- (continued)

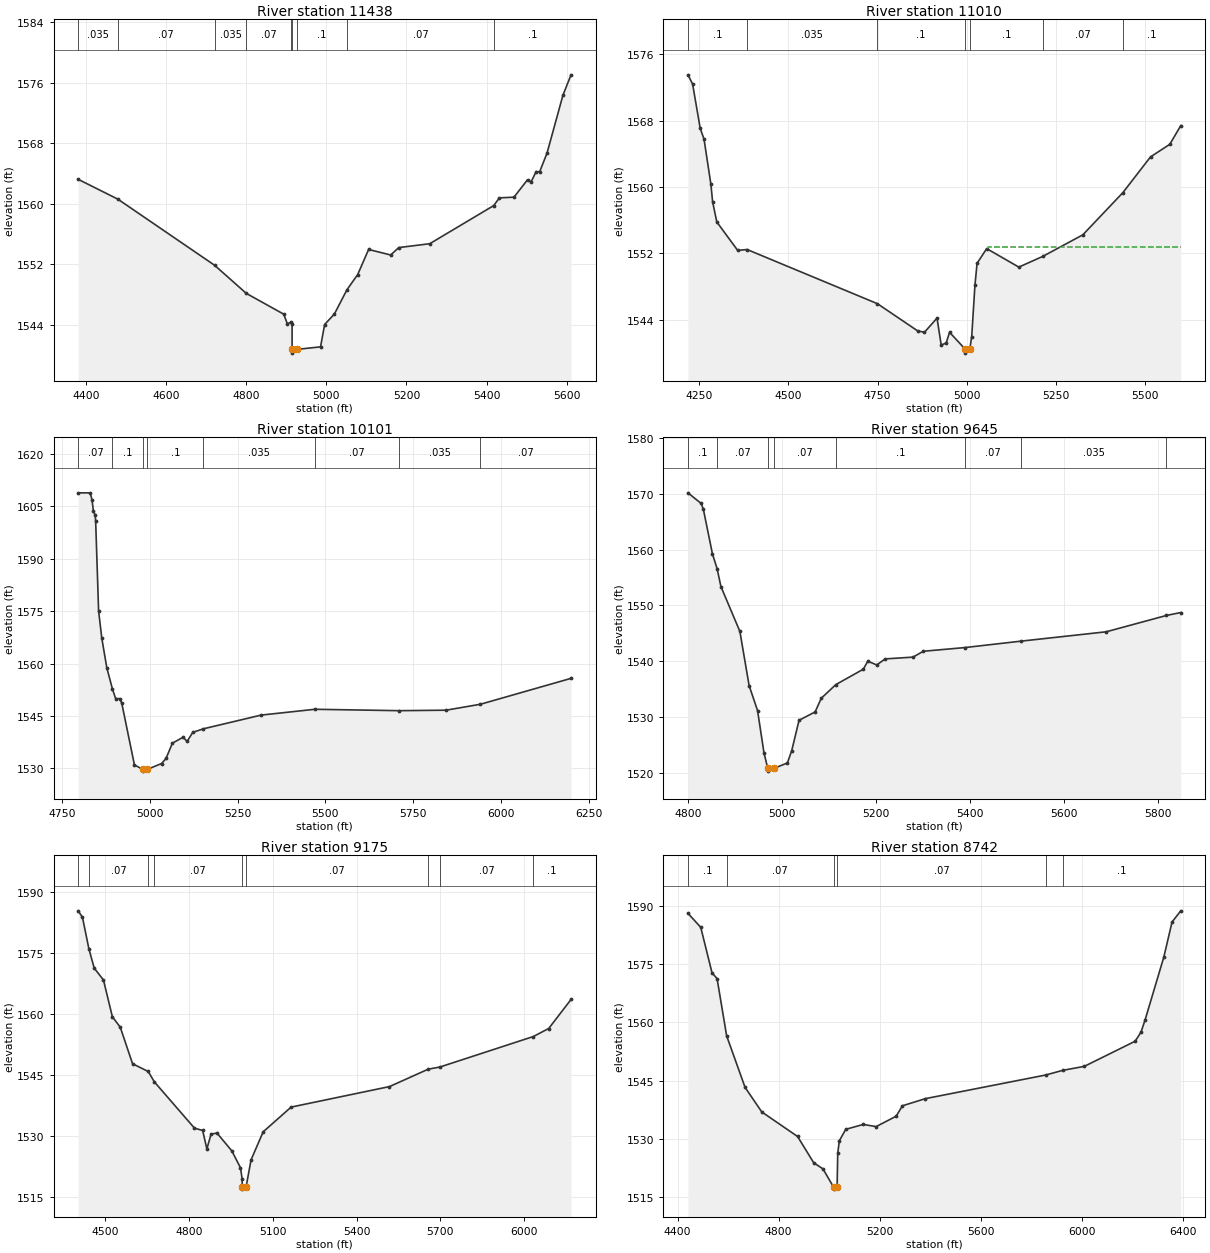
Type RM Length L Ch R = 1 ,11438   ,428,428,428
BEGIN DESCRIPTION:
Elm Creek 22.0
END DESCRIPTION:
XS GIS Cut Line= 3
        1963875.       13877675.      1964420.61     13877960.98
      1965025.03     13878075.01
#Sta/Elev= 30
  4379.9 1563.21    4479 1560.59  4720.7 1551.85    4800 1548.13  4893.3 1545.39
  4902.5  1544.1  4911.1 1544.33  4914.2 1544.08  4914.3 1540.74  4914.8 1540.24
  4927.6 1540.74  4985.3 1541.07  4995.5 1544.02  5019.9 1545.41  5051.2 1548.61
  5078.1 1550.62  5105.4 1553.94  5160.4 1553.21  5180.8 1554.19  5258.1  1554.7
  5417.9 1559.74  5432.1 1560.76  5468.5 1560.85  5502.3 1563.15  5511.4 1562.87
  5523.7 1564.22  5532.7 1564.21  5551.1 1566.68  5590.8 1574.32    5611 1577.02
#Mann= 9 ,-1 , 0
  4379.9    .035       0    4479     .07       0  4720.7    .035       0
    4800     .07       0  4911.1      .1       0  4914.3     .05       0
  4927.6      .1       0  5051.2     .07       0  5417.9      .1       0
Bank Sta=4914.3,4927.6
XS Rating Curve= 0 ,0
Exp/Cntr=0.3,0.1

Type RM Length L Ch R = 1 ,11010   ,909,909,909
BEGIN DESCRIPTION:
Elm Creek 21.0
END DESCRIPTION:
XS GIS Cut Line= 3
      1963725.02     13877825.02        1964325.       13878325.
        1964925.       13878325.
#Sta/Elev= 30
  4218.5 1573.53  4231.6 1572.42  4252.9 1567.07  4263.6 1565.78  4282.8 1560.35
  4287.7 1558.21  4299.4 1555.79    4358 1552.36  4384.3 1552.47  4749.5 1545.94
  4862.6 1542.65  4881.3  1542.5  4916.5  1544.2  4928.2 1540.95  4942.2 1541.21
  4951.6 1542.49    4995 1540.48  4995.5 1539.98  5008.4 1540.48  5013.7 1541.98
  5022.7 1548.14  5028.7 1550.81  5055.7 1552.58  5145.7 1550.35  5212.7 1551.64
    5325 1554.24  5437.1 1559.32  5514.7 1563.64  5568.7 1565.15  5599.5 1567.41
#Mann= 7 ,-1 , 0
  4218.5      .1       0  4384.3    .035       0  4749.5      .1       0
    4995     .05       0  5008.4      .1       0  5212.7     .07       0
  5437.1      .1       0
#XS Ineff= 2 , 0
                         5058.74          1552.8
Permanent Ineff=
       F       F
Bank Sta=4995,5008.4
XS Rating Curve= 0 ,0
Exp/Cntr=0.3,0.1

Type RM Length L Ch R = 1 ,10101   ,456,456,456
BEGIN DESCRIPTION:
Elm Creek 20.0
END DESCRIPTION:
XS GIS Cut Line= 3
      1963375.03       13878625.        1963575.       13878625.
      1964774.97       13878725.
#Sta/Elev= 30
    4796 1608.83  4830.2 1608.85  4835.5 1606.78  4839.2 1603.77  4844.5 1602.41
  4845.8 1600.68  4854.2 1575.03  4863.2 1567.29  4877.5  1558.8  4893.6 1552.71
  4902.8 1549.94  4914.2 1549.95  4920.2 1548.62  4956.2    1531  4979.5  1529.7
    4980  1529.2  4992.9  1529.7  5033.5 1531.37  5046.3 1532.83  5064.4  1537.2
  5094.5 1538.88  5106.5 1537.72  5122.4 1540.29    5153 1541.32  5317.3 1545.24
  5470.5  1546.9  5710.5  1546.5  5844.1 1546.64    5942 1548.34  6200.1 1555.75
#Mann= 8 ,-1 , 0
    4796     .07       0  4893.6      .1       0  4979.5     .05       0
  4992.9      .1       0    5153    .035       0  5470.5     .07       0
  5710.5    .035       0    5942     .07       0
Bank Sta=4979.5,4992.9
XS Rating Curve= 0 ,0
Exp/Cntr=0.3,0.1

Type RM Length L Ch R = 1 ,9645    ,470,470,470
BEGIN DESCRIPTION:
Elm Creek 19.0
END DESCRIPTION:
XS GIS Cut Line= 3
      1963524.96       13879025.        1963725.       13879025.
      1964544.02     13878801.52
#Sta/Elev= 30
    4800 1570.17  4828.2 1568.26  4832.9  1567.2  4852.2  1559.2  4862.1 1556.57
  4870.2 1553.36  4910.6  1545.3  4930.2  1535.6  4948.2 1531.11  4961.9 1523.51
  4969.9 1520.75  4970.4 1520.25  4983.3 1520.75  5011.7 1521.71    5021 1523.95
  5036.5 1529.37  5070.7 1530.87  5083.8 1533.32  5114.8 1535.77  5173.4 1538.54
  5182.7 1539.97  5201.8  1539.3    5220 1540.38  5279.1  1540.7  5300.9 1541.75
  5389.1 1542.41  5509.5 1543.57  5690.1 1545.24  5818.4 1548.17    5849  1548.7
#Mann= 8 ,-1 , 0
    4800      .1       0  4862.1     .07       0  4969.9     .05       0
  4983.3     .07       0  5114.8      .1       0  5389.1     .07       0
  5509.5    .035       0  5818.4     .07       0
Bank Sta=4969.9,4983.3
XS Rating Curve= 0 ,0
Exp/Cntr=0.3,0.1

Type RM Length L Ch R = 1 ,9175    ,433,433,433
BEGIN DESCRIPTION:
Elm Creek 18.0
END DESCRIPTION:
XS GIS Cut Line= 3
        1963325.       13879375.        1963925.       13879425.
      1964969.97     13878915.36
#Sta/Elev= 30
  4403.2 1585.43  4418.5 1583.84  4441.4 1576.11  4460.6 1571.31  4493.7 1568.39
  4525.6 1559.34  4553.9 1556.75  4597.9 1547.76    4654 1545.85    4676 1543.29
  4819.6 1531.89  4848.9 1531.32    4864 1526.77    4879 1530.42  4900.1 1530.68
    4953 1526.33  4984.4 1522.13  4990.4 1519.34  4990.5 1517.37    4991 1516.87
  5004.3 1517.37  5022.2 1524.08  5065.6 1530.99  5165.7 1537.08  5517.8 1542.13
  5656.6 1546.42  5698.3 1546.95  6032.8 1554.46    6088 1556.44  6167.9 1563.59
#Mann= 9 ,-1 , 0
  4403.2    .035       0  4441.4     .07       0    4654      .1       0
    4676     .07       0  4990.5     .05       0  5004.3     .07       0
  5656.6    .035       0  5698.3     .07       0  6032.8      .1       0
Bank Sta=4990.5,5004.3
XS Rating Curve= 0 ,0
Exp/Cntr=0.3,0.1

Type RM Length L Ch R = 1 ,8742    ,945,945,945
BEGIN DESCRIPTION:
Elm Creek 17.0
END DESCRIPTION:
XS GIS Cut Line= 4
      1963525.01     13880074.99        1964025.       13879825.
        1964325.       13879725.       1965319.1     13879314.91
#Sta/Elev= 30
    4441 1588.06  4491.7 1584.44  4536.2 1572.78  4556.4 1571.24  4594.2 1556.53
  4667.1 1543.28  4733.2 1536.96    4875 1530.64  4938.7 1523.89  4975.6  1522.3
  5017.5  1517.6    5018  1517.1  5031.4  1517.6  5033.9 1526.35  5040.3 1529.55
  5065.6 1532.48  5135.1 1533.74  5185.7 1533.18  5264.8 1535.84  5290.1 1538.54
  5380.3 1540.37  5856.5 1546.45  5924.2 1547.65  6009.8 1548.68  6211.1 1555.15
  6234.3  1557.5    6250 1560.55  6324.6 1576.81  6357.1 1585.82  6391.6 1588.69
#Mann= 6 ,-1 , 0
    4441      .1       0  4594.2     .07       0  5017.5     .05       0
  5031.4     .07       0  5856.5    .035       0  5924.2      .1       0
Bank Sta=5017.5,5031.4
XS Rating Curve= 0 ,0
Exp/Cntr=0.3,0.1

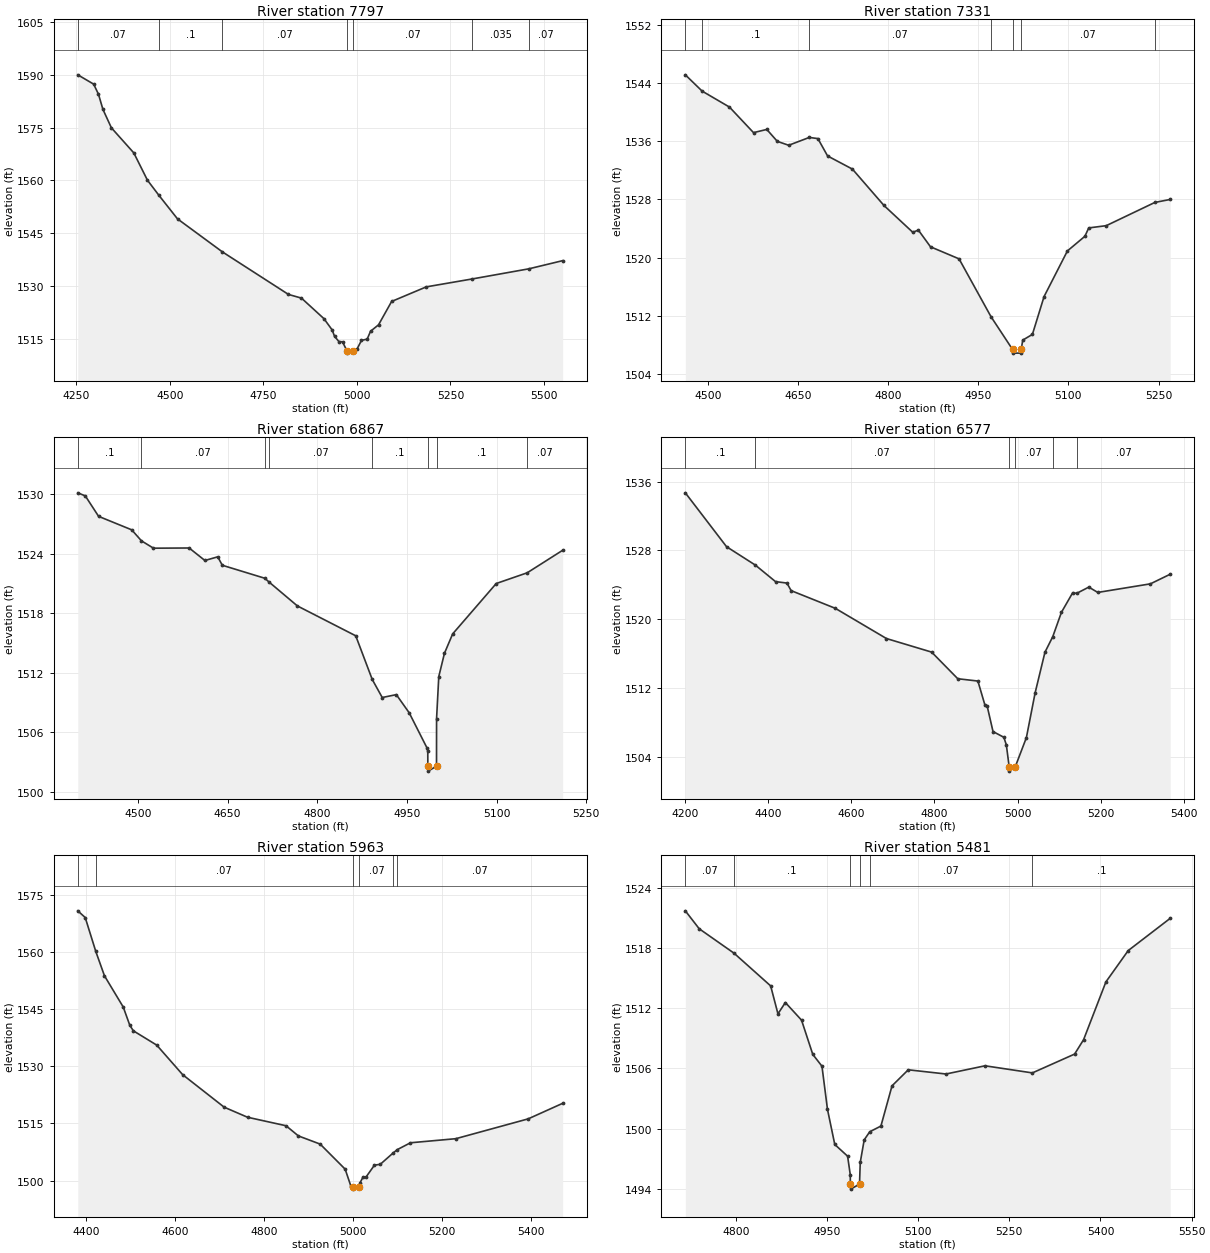
Type RM Length L Ch R = 1 ,7797    ,466,466,466
BEGIN DESCRIPTION:
Elm Creek 16.0
END DESCRIPTION:
XS GIS Cut Line= 3
      1963365.77     13880494.01        1964075.       13880725.
      1964618.45      13880640.4
#Sta/Elev= 30
    4254 1589.99  4296.5 1587.34  4309.3 1584.47  4321.2 1580.17  4343.8 1574.94
  4403.8  1567.8  4440.2 1560.05  4470.6 1555.79  4520.5 1549.07  4640.5 1539.69
  4817.1  1527.6  4851.8 1526.56  4911.8 1520.73  4933.9 1517.51  4940.2 1515.71
  4951.9 1514.21  4961.5 1514.15    4974 1511.43  4974.5 1510.93  4988.3 1511.43
  5000.1 1512.04  5012.2 1514.55  5027.4 1514.91  5036.5 1517.15  5057.8 1518.97
  5092.8 1525.61  5185.3 1529.75  5308.6 1532.01  5459.5 1534.88  5549.9  1537.2
#Mann= 7 ,-1 , 0
    4254     .07       0  4470.6      .1       0  4640.5     .07       0
    4974     .05       0  4988.3     .07       0  5308.6    .035       0
  5459.5     .07       0
Bank Sta=4974,4988.3
XS Rating Curve= 0 ,0
Exp/Cntr=0.3,0.1

Type RM Length L Ch R = 1 ,7331    ,464,464,464
BEGIN DESCRIPTION:
Elm Creek 15.0
END DESCRIPTION:
XS GIS Cut Line= 3
      1963601.75     13881053.05        1964125.       13881175.
      1964374.97     13881075.01
#Sta/Elev= 30
  4462.8 1545.16  4490.7 1542.92  4536.2 1540.72  4576.2  1537.2  4598.3 1537.64
  4615.8    1536  4634.7 1535.46    4669 1536.54  4683.3 1536.38  4699.4 1533.99
  4740.7 1532.18  4793.2 1527.17  4841.1 1523.48  4850.4 1523.78  4870.6 1521.48
  4918.1 1519.82  4971.2 1511.86  5007.1 1507.34  5007.6 1506.84    5021 1506.84
  5021.5 1507.34    5024 1508.63  5040.1 1509.42  5059.5 1514.63  5098.3 1520.91
  5127.4 1522.93  5133.8 1524.08  5162.9 1524.39  5243.8 1527.59  5269.3    1528
#Mann= 7 ,-1 , 0
  4462.8     .07       0  4490.7      .1       0    4669     .07       0
  4971.2     .07       0  5007.1     .05       0  5021.5     .07       0
  5243.8    .035       0
Bank Sta=5007.1,5021.5
XS Rating Curve= 0 ,0
Exp/Cntr=0.3,0.1

Type RM Length L Ch R = 1 ,6867    ,290,290,290
BEGIN DESCRIPTION:
Elm Creek 14.0
END DESCRIPTION:
XS GIS Cut Line= 3
      1963683.94     13881271.91        1964175.       13881625.
      1964375.02     13881574.99
#Sta/Elev= 30
  4399.4 1530.15    4412 1529.84  4434.2 1527.78  4489.6 1526.42  4505.9 1525.31
    4526 1524.57  4585.7 1524.59    4612 1523.33  4633.5  1523.7  4641.1 1522.85
  4712.2 1521.54  4719.5 1521.15  4766.7 1518.75  4864.3 1515.74  4891.9 1511.34
  4908.6 1509.52  4932.2 1509.81  4953.7 1507.98  4983.8  1504.4  4984.8  1504.1
  4984.9  1502.6  4985.4  1502.1  4999.4  1502.6  4999.5 1507.39  5003.2 1511.63
  5012.7 1513.98  5026.4 1515.93  5099.3 1521.01  5151.1 1522.09  5210.4 1524.36
#Mann= 8 ,-1 , 0
  4399.4      .1       0  4505.9     .07       0  4712.2    .035       0
  4719.5     .07       0  4891.9      .1       0  4984.9     .05       0
  4999.4      .1       0  5151.1     .07       0
Bank Sta=4984.9,4999.4
XS Rating Curve= 0 ,0
Exp/Cntr=0.3,0.1

Type RM Length L Ch R = 1 ,6577    ,614,614,614
BEGIN DESCRIPTION:
Elm Creek 13.0
END DESCRIPTION:
XS GIS Cut Line= 3
        1963425.       13881425.      1964037.85     13881878.06
       1964440.7     13881916.38
#Sta/Elev= 30
  4200.5 1534.71  4299.6 1528.44  4369.1 1526.29  4417.5 1524.37    4445  1524.2
  4455.1 1523.32  4561.4 1521.26  4684.5 1517.74  4793.2 1516.16  4856.1 1513.06
  4904.5 1512.79  4921.6 1509.97    4927 1509.84  4940.9 1506.91    4967 1506.24
    4973 1505.35  4979.8  1502.8  4980.3  1502.3  4994.4  1502.8  5021.2  1506.2
  5042.3 1511.43  5065.9 1516.15  5084.7 1517.96  5105.6  1520.8  5132.7 1523.08
  5142.1    1523  5171.4 1523.73    5193 1523.11  5319.6 1524.11  5367.3 1525.23
#Mann= 6 ,-1 , 0
  4200.5      .1       0  4369.1     .07       0  4979.8     .05       0
  4994.4     .07       0  5084.7      .1       0  5142.1     .07       0
Bank Sta=4979.8,4994.4
XS Rating Curve= 0 ,0
Exp/Cntr=0.3,0.1

Type RM Length L Ch R = 1 ,5963    ,482,482,482
BEGIN DESCRIPTION:
Elm Creek 12.0
END DESCRIPTION:
XS GIS Cut Line= 3
      1963374.97     13882575.01        1963975.       13882425.
        1964375.       13882175.
#Sta/Elev= 30
  4381.6 1570.77  4398.3 1569.01  4422.1 1560.11  4441.6 1553.72  4483.8 1545.53
  4498.6 1540.73  4506.6 1539.29  4559.1 1535.54  4617.4 1527.79  4710.7 1519.26
  4763.2 1516.62  4849.8 1514.39  4877.6 1511.72  4926.6 1509.57  4982.8 1502.99
  4995.2  1498.7  4999.8 1498.26  5000.3 1497.76  5014.8 1498.26  5015.7 1499.32
  5022.7 1500.86  5029.8 1500.95  5048.6 1504.05  5061.7 1504.27  5091.4 1507.32
  5099.9 1508.12  5129.6 1509.92  5231.5 1510.99  5394.2 1516.19  5471.8 1520.27
#Mann= 6 ,-1 , 0
  4381.6      .1       0  4422.1     .07       0  4999.8     .05       0
  5014.8     .07       0  5091.4      .1       0  5099.9     .07       0
Bank Sta=4999.8,5014.8
XS Rating Curve= 0 ,0
Exp/Cntr=0.3,0.1

Type RM Length L Ch R = 1 ,5481    ,434,434,434
BEGIN DESCRIPTION:
Elm Creek 11.0
END DESCRIPTION:
XS GIS Cut Line= 3
      1963788.54     13882904.05        1964075.       13882875.
      1964574.97     13882775.01
#Sta/Elev= 30
  4716.9 1521.75  4739.7 1519.96    4797 1517.52  4857.3 1514.25  4869.3 1511.46
  4881.5 1512.59  4908.1 1510.83  4926.6 1507.41  4941.7 1506.23  4950.8 1501.91
  4962.8 1498.41  4983.9 1497.24  4988.3 1495.38  4988.4 1494.45  4988.9 1493.95
  5003.5 1494.45  5004.7 1496.62  5011.2 1498.87  5020.3 1499.68  5038.7 1500.25
    5057 1504.27  5083.7 1505.87  5145.8 1505.45    5210 1506.27  5287.9 1505.56
  5357.4 1507.44  5372.2 1508.88  5408.9 1514.65  5445.6 1517.78  5514.7    1521
#Mann= 6 ,-1 , 0
  4716.9     .07       0    4797      .1       0  4988.4     .05       0
  5003.5      .1       0  5020.3     .07       0  5287.9      .1       0
Bank Sta=4988.4,5003.5
XS Rating Curve= 0 ,0
Exp/Cntr=0.3,0.1

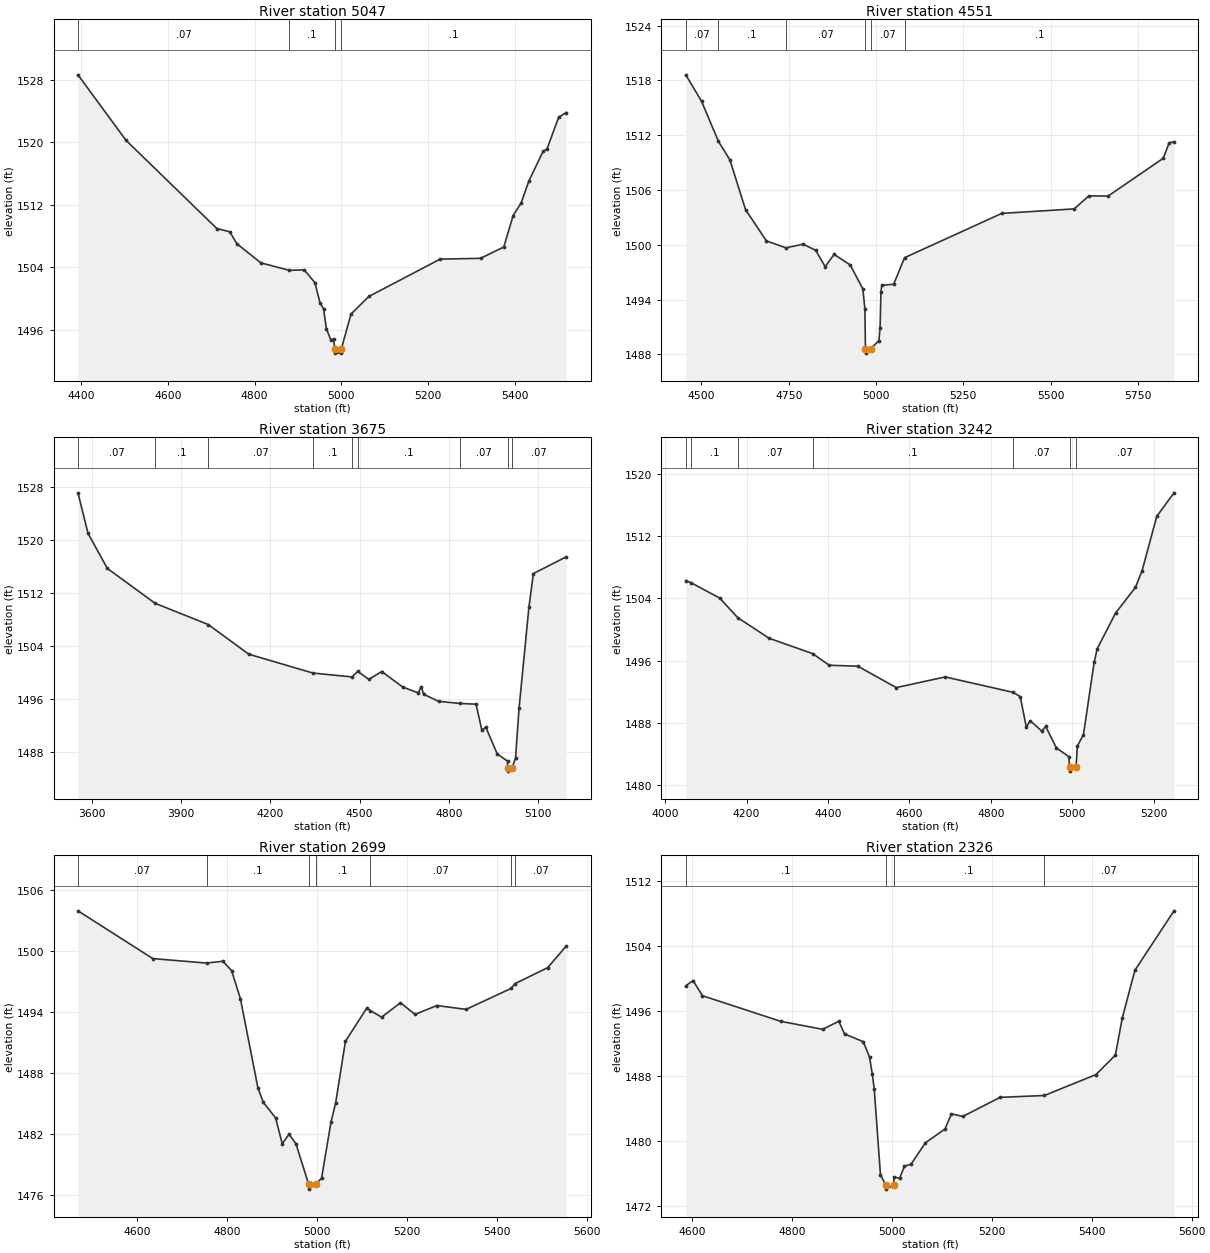
Type RM Length L Ch R = 1 ,5047    ,496,496,496
BEGIN DESCRIPTION:
Elm Creek 10.0
END DESCRIPTION:
XS GIS Cut Line= 4
      1963674.97       13883225.      1964213.54     13883269.88
      1964308.27     13883225.09      1964575.02     13882824.97
#Sta/Elev= 30
  4392.4 1528.63  4503.2 1520.26  4712.7 1508.98  4742.8 1508.56  4758.8 1507.04
  4814.4 1504.59  4880.2 1503.63  4914.4  1503.7  4939.1 1502.04  4950.5 1499.52
    4959 1498.68  4965.6 1496.13  4975.6 1494.77  4982.2 1494.83  4984.6 1493.55
  4985.1 1493.05  4999.3 1493.05  4999.8 1493.55  5022.1 1498.04  5063.3 1500.29
  5227.8 1505.07    5321 1505.17  5374.6 1506.62  5396.2 1510.64  5414.7 1512.26
  5432.7  1515.1  5465.2 1518.83  5474.4 1519.17  5501.2 1523.21  5518.5 1523.81
#Mann= 4 ,-1 , 0
  4392.4     .07       0  4880.2      .1       0  4984.6     .05       0
  4999.8      .1       0
Bank Sta=4984.6,4999.8
XS Rating Curve= 0 ,0
Exp/Cntr=0.3,0.1

Type RM Length L Ch R = 1 ,4551    ,876,876,876
BEGIN DESCRIPTION:
Elm Creek 9.0
END DESCRIPTION:
XS GIS Cut Line= 3
      1963924.96       13883675.        1964475.       13883675.
      1965075.02     13883074.98
#Sta/Elev= 30
    4455 1518.61  4500.2 1515.71  4548.5 1511.33  4581.2 1509.31  4626.2 1503.85
  4686.2 1500.42  4741.7 1499.67  4791.2 1500.07  4827.2  1499.4  4854.2 1497.61
  4879.9 1498.95  4926.2 1497.79  4962.2 1495.17  4968.2 1492.93  4969.6 1488.64
  4970.1 1488.14  4984.9 1488.64  5008.1  1489.5  5011.6 1490.94  5014.1 1494.88
  5016.6 1495.56  5050.6 1495.69  5081.7 1498.59  5360.3 1503.44  5567.4 1503.93
  5609.8 1505.36    5665 1505.34  5822.7 1509.47  5839.7 1511.17  5853.6 1511.28
#Mann= 6 ,-1 , 0
    4455     .07       0  4548.5      .1       0  4741.7     .07       0
  4969.6     .05       0  4984.9     .07       0  5081.7      .1       0
Bank Sta=4969.6,4984.9
XS Rating Curve= 0 ,0
Exp/Cntr=0.3,0.1

Type RM Length L Ch R = 1 ,3675    ,433,433,433
BEGIN DESCRIPTION:
Elm Creek 8.0
END DESCRIPTION:
XS GIS Cut Line= 3
      1963975.02     13884574.99        1965175.       13883775.
        1965175.       13883575.
#Sta/Elev= 30
  3552.7 1527.08  3586.6 1520.96  3651.5 1515.68  3812.3 1510.41  3990.9 1507.21
  4127.4 1502.73  4342.9 1499.89  4474.9  1499.3  4493.6 1500.14  4531.2 1498.94
  4574.5 1500.12  4645.1 1497.78  4697.1  1496.9  4707.6 1497.84  4715.1  1496.7
  4765.6 1495.62  4837.9  1495.3  4891.8 1495.19  4911.1  1491.3  4924.7  1491.7
  4963.1 1487.67  4997.6  1486.6  4997.7 1485.59  4998.2 1485.09  5013.1 1485.59
  5024.6 1487.09  5036.6 1494.66  5069.6 1509.82  5084.6  1514.9  5194.9 1517.42
#Mann= 9 ,-1 , 0
  3552.7     .07       0  3812.3      .1       0  3990.9     .07       0
  4342.9      .1       0  4474.9     .07       0  4493.6      .1       0
  4837.9     .07       0  4997.7     .05       0  5013.1     .07       0
Bank Sta=4997.7,5013.1
XS Rating Curve= 0 ,0
Exp/Cntr=0.3,0.1

Type RM Length L Ch R = 1 ,3242    ,543,543,543
BEGIN DESCRIPTION:
Elm Creek 7.0
END DESCRIPTION:
XS GIS Cut Line= 3
      1964424.96     13884425.01        1965325.       13884125.
      1965524.98     13883975.01
#Sta/Elev= 30
  4050.8  1506.3  4063.1 1506.04  4134.3 1504.04  4178.3 1501.53  4255.3 1498.88
  4362.3  1496.9  4403.1  1495.4  4472.9 1495.29  4567.6 1492.53  4687.7  1493.9
  4855.1 1491.91    4872 1491.36  4886.9 1487.44  4896.4 1488.27  4924.9 1486.93
  4934.4 1487.53  4960.8 1484.77  4991.3 1483.64  4993.1 1482.28  4993.6 1481.78
    5009 1482.28  5012.2 1485.01  5027.2 1486.48  5053.5  1495.8    5061 1497.53
    5106 1502.12  5154.8 1505.42  5170.9 1507.53  5207.2 1514.57  5249.5 1517.59
#Mann= 7 ,-1 , 0
  4050.8     .07       0  4063.1      .1       0  4178.3     .07       0
  4362.3      .1       0  4855.1     .07       0  4993.1     .05       0
    5009     .07       0
Bank Sta=4993.1,5009
XS Rating Curve= 0 ,0
Exp/Cntr=0.3,0.1

Type RM Length L Ch R = 1 ,2699    ,373,373,373
BEGIN DESCRIPTION:
Elm Creek 6.0
END DESCRIPTION:
XS GIS Cut Line= 4
      1964484.79     13884488.48      1964961.68     13884466.92
       1965048.2     13884499.84      1965526.22     13884697.17
#Sta/Elev= 30
  4467.5 1503.93  4634.1 1499.24  4753.8  1498.8  4790.2 1498.98  4809.6 1498.06
  4829.3 1495.29  4868.3 1486.53  4880.3 1485.11  4907.6  1483.6  4922.4 1481.05
  4937.4 1481.99  4952.9 1481.06    4981  1477.1  4981.5  1476.6    4997  1477.1
  5009.9 1477.67  5030.9 1483.17  5041.4 1485.09  5063.1 1491.12    5111  1494.4
  5118.6 1494.14  5143.5 1493.49  5185.7  1494.9  5218.1 1493.76  5266.8 1494.63
  5331.7 1494.25  5432.8 1496.33  5439.8 1496.76  5513.4 1498.35  5554.6 1500.46
#Mann= 7 ,-1 , 0
  4467.5     .07       0  4753.8      .1       0    4981     .05       0
    4997      .1       0  5118.6     .07       0  5432.8    .035       0
  5439.8     .07       0
Bank Sta=4981,4997
XS Rating Curve= 0 ,0
Exp/Cntr=0.3,0.1

Type RM Length L Ch R = 1 ,2326    ,482,482,482
BEGIN DESCRIPTION:
Elm Creek 5.0
END DESCRIPTION:
XS GIS Cut Line= 3
      1964529.27     13884709.74        1964925.       13884825.
      1965446.53     13885041.34
#Sta/Elev= 30
  4587.9  1499.1  4602.4 1499.74  4621.2 1497.88  4777.4 1494.73  4861.7 1493.74
    4894 1494.73  4905.5 1493.17    4943 1492.22  4955.5 1490.32    4961 1488.25
  4964.9 1486.42  4977.4 1475.82  4988.1 1474.56  4988.6 1474.06  5004.1 1474.56
  5004.3 1475.59  5015.5 1475.38  5025.2 1476.86  5038.8 1477.15  5067.4 1479.77
  5106.4 1481.46  5119.4 1483.33  5142.1 1483.01  5216.8 1485.36  5305.3 1485.59
  5408.4 1488.16  5447.4 1490.56  5461.1  1495.1  5486.4    1501  5564.7 1508.33
#Mann= 4 ,-1 , 0
  4587.9      .1       0  4988.1     .05       0  5004.1      .1       0
  5305.3     .07       0
Bank Sta=4988.1,5004.1
XS Rating Curve= 0 ,0
Exp/Cntr=0.3,0.1

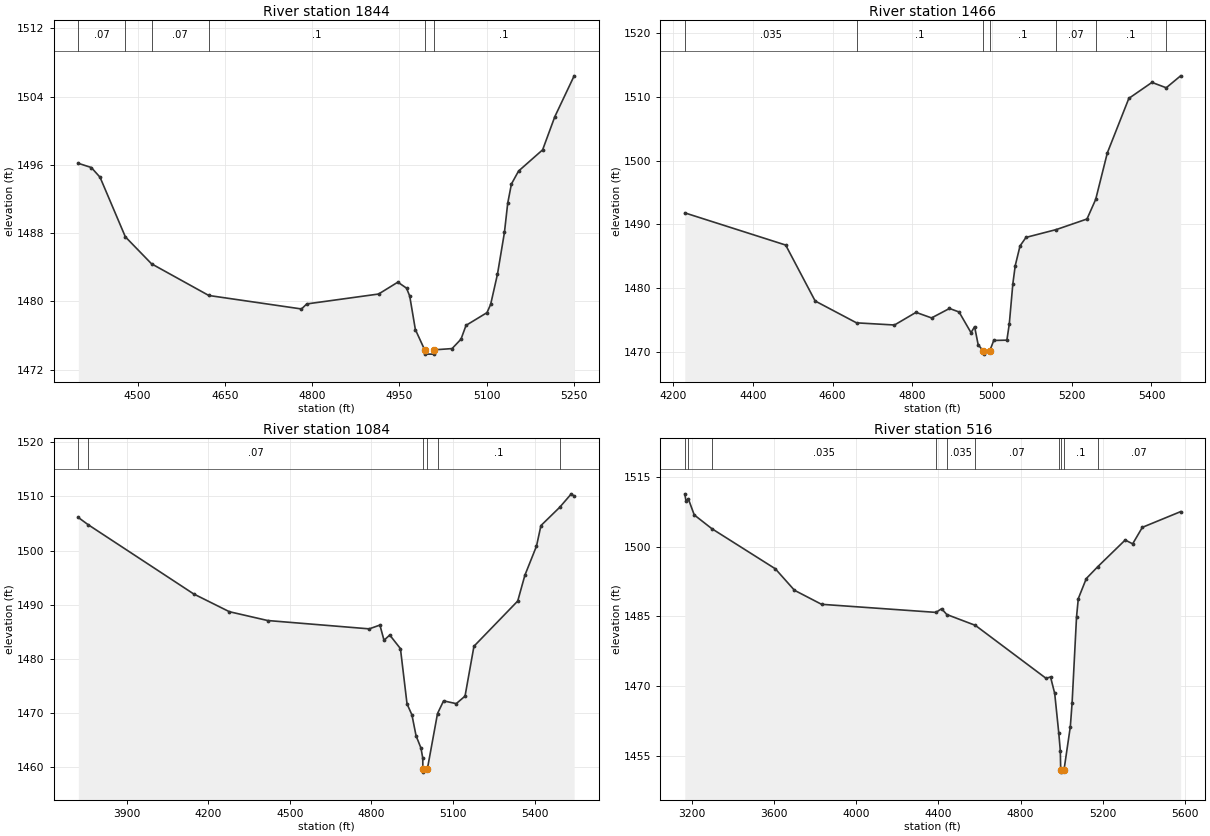
Type RM Length L Ch R = 1 ,1844    ,378,378,378
BEGIN DESCRIPTION:
Elm Creek 4.0
END DESCRIPTION:
XS GIS Cut Line= 3
      1964424.99       13885325.        1965025.       13885275.
      1965275.01       13885275.
#Sta/Elev= 30
  4398.3 1496.18  4420.6 1495.69  4435.6 1494.55  4479.1 1487.57  4524.1 1484.41
  4622.5  1480.7  4781.8 1479.12  4790.9 1479.71  4914.3 1480.87  4947.4 1482.26
  4962.3 1481.56  4967.8 1480.63  4977.5 1476.71  4993.5 1474.33    4994 1473.83
  5009.1 1473.83  5009.6 1474.33  5040.6 1474.48  5055.9 1475.58  5064.6  1477.2
  5100.6 1478.69  5106.9 1479.66  5118.6 1483.19  5130.6 1488.09  5136.2  1491.5
  5142.6 1493.76  5154.9 1495.28  5196.2 1497.76  5217.2 1501.65  5250.4 1506.43
#Mann= 6 ,-1 , 0
  4398.3     .07       0  4479.1      .1       0  4524.1     .07       0
  4622.5      .1       0  4993.5     .05       0  5009.6      .1       0
Bank Sta=4993.5,5009.6
XS Rating Curve= 0 ,0
Exp/Cntr=0.3,0.1

Type RM Length L Ch R = 1 ,1466    ,382,382,382
BEGIN DESCRIPTION:
Elm Creek 3.0
END DESCRIPTION:
XS GIS Cut Line= 3
      1964254.14     13885596.93      1965047.26     13885605.05
      1965498.08      13885600.7
#Sta/Elev= 30
  4229.2 1491.82  4482.3 1486.78  4556.3 1478.02    4660  1474.6  4755.3 1474.26
  4809.3 1476.24  4848.3 1475.37  4893.3 1476.85  4917.3  1476.3  4947.3 1473.06
  4956.3    1474  4965.3 1471.15  4978.2  1470.2  4978.7  1469.7  4994.3  1470.2
  5004.3 1471.84  5037.3 1471.89  5043.3  1474.4  5052.3 1480.74  5058.3 1483.57
  5070.3 1486.65  5085.3 1487.98  5161.5 1489.21  5238.3 1490.86  5260.1 1493.93
  5289.3 1501.21  5343.3 1509.75  5401.3 1512.25  5437.1 1511.41  5473.2 1513.28
#Mann= 7 ,-1 , 0
  4229.2    .035       0    4660      .1       0  4978.2     .05       0
  4994.3      .1       0  5161.5     .07       0  5260.1      .1       0
  5437.1     .07       0
Bank Sta=4978.2,4994.3
XS Rating Curve= 0 ,0
Exp/Cntr=0.3,0.1

Type RM Length L Ch R = 1 ,1084    ,568,568,568
BEGIN DESCRIPTION:
Elm Creek 2.0
END DESCRIPTION:
XS GIS Cut Line= 4
       1963774.7     13885613.59      1964764.89     13885966.08
        1964998.     13885938.55       1965488.7     13885719.89
#Sta/Elev= 30
  3722.8  1506.1  3758.9 1504.77  4146.9 1491.98    4278  1488.7  4418.9 1487.07
  4792.3 1485.53  4831.6 1486.23  4846.7 1483.42  4867.8 1484.39  4907.1 1481.88
  4931.3 1471.68  4949.4 1469.63  4964.5 1465.79  4982.6 1463.51  4989.2 1461.64
  4989.6 1459.57  4990.1 1459.07  5005.8 1459.57  5043.4 1469.89  5065.7 1472.23
  5112.3 1471.72  5144.6 1473.11  5177.4 1482.32  5338.3 1490.67  5364.6 1495.43
  5407.3 1500.81  5423.7 1504.61  5492.4 1507.97  5535.4 1510.47  5545.8 1510.04
#Mann= 6 ,-1 , 0
  3722.8     .07       0  3758.9     .07       0  4989.6     .05       0
  5005.8     .07       0  5043.4      .1       0  5492.4     .07       0
Bank Sta=4989.6,5005.8
XS Rating Curve= 0 ,0
Exp/Cntr=0.3,0.1

Type RM Length L Ch R = 1 ,516     ,0,0,0
BEGIN DESCRIPTION:
Elm Creek 1.0
END DESCRIPTION:
XS GIS Cut Line= 5
      1963691.35     13885627.47      1965223.86       13886325.
        1965375.       13886325.       1965510.6     13886184.85
      1965676.95      13885838.9
#Sta/Elev= 30
    3165 1511.38  3170.8 1509.82  3182.2  1510.3    3211 1506.84  3296.4 1503.89
  3605.7 1495.25  3698.8 1490.63  3830.7 1487.61  4387.8 1485.87  4415.1 1486.66
  4440.5 1485.41  4579.5 1483.08  4923.8 1471.68  4945.5 1471.98  4965.8 1468.43
  4985.6 1459.92  4993.1 1456.08    4995    1452  4995.5  1451.5  5011.2    1452
  5041.9  1461.3  5050.5 1466.41  5072.1 1484.92  5080.7 1488.84  5119.6 1493.15
  5174.9 1495.68  5308.9 1501.44  5345.3 1500.62  5392.5 1504.17  5578.8 1507.55
#Mann= 10 ,-1 , 0
    3165      .1       0  3182.2     .07       0  3296.4    .035       0
  4387.8     .07       0  4440.5    .035       0  4579.5     .07       0
  4985.6      .1       0    4995     .05       0  5011.2      .1       0
  5174.9     .07       0
Bank Sta=4995,5011.2
XS Rating Curve= 0 ,0
Exp/Cntr=0.3,0.1

Chan Stop Cuts=-1
Use User Specified Reach Order=0
Composite Channel Slope=5