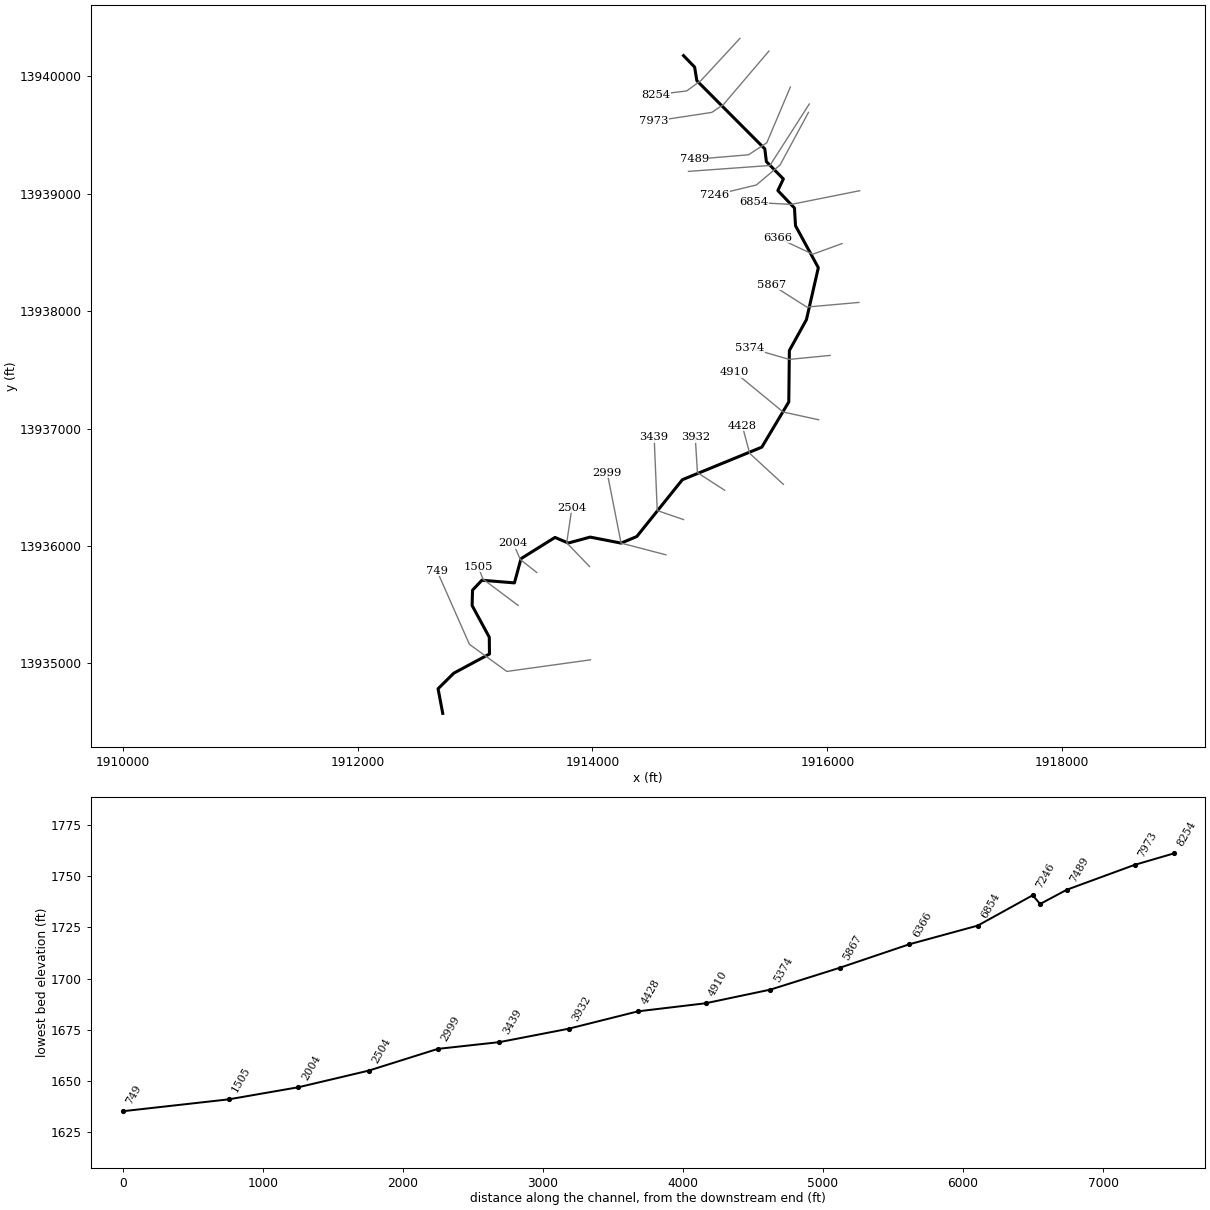
--- Elm Creek_2.prj (project) ---

Proj Title=Elm Creek_2 Base Level Engineering
Current Plan=p01
Default Exp/Contr=0.3,0.1
English Units
Geom File=g01
Flow File=f01
Plan File=p01
Y Axis Title=Elevation
X Axis Title(PF)=Main Channel Distance
X Axis Title(XS)=Station
BEGIN DESCRIPTION:
Elm Creek_2
END DESCRIPTION:
DSS Export Rating Curves= 0
DSS Export Rating Curve Sorted= 0
DSS Export Volume Flow Curves= 0
DXF OffsetX= 0
DXF OffsetY= 0
DXF ScaleX= 1
DXF ScaleY= 10

--- Elm Creek_2.p01 (plan) ---

Plan Title=Multiple Run
Short Identifier=Multiple
Geom File=g01
Flow File=f01
Subcritical Flow
K Sum by GR= 0
Std Step Tol= 0.01
Critical Tol= 0.01
Num of Std Step Trials= 20
Max Error Tol= 0.3
Flow Tol Ratio= 0.001
Split Flow NTrial= 30
Split Flow Tol= 0.02
Split Flow Ratio= 0.02
Log Output Level= 0
Friction Slope Method= 1
Unsteady Friction Slope Method= 2
Unsteady Bridges Friction Slope Method= 1
Parabolic Critical Depth
Global Vel Dist=  1 , 1 , 1
Global Log Level= 0
CheckData=True
Encroach Param= -1, 0, 0, 0
BEGIN DESCRIPTION:
Multiple Run
END DESCRIPTION:

--- Elm Creek_2.f01 (steady flow) ---

Flow Title=Multiple
Program Version=4.10
Number of Profiles= 7
Profile Names=10-year,25-year,50-year,1pct_min,100-year,1pct_plu,500-year
River Rch & RM=Elm Creek_2,Reach-1         ,8254
     386     617     824     536    1070    2135    1772
River Rch & RM=Elm Creek_2,Reach-1         ,6366
    1069    1840    2583    1757    3507    6996    6374
River Rch & RM=Elm Creek_2,Reach-1         ,5374
    1196    2068    2911    1985    3960    7901    7228
River Rch & RM=Elm Creek_2,Reach-1         ,4428
    1519    2648    3747    2563    5115   10205    9410
Boundary for River Rch & Prof#=Elm Creek_2,Reach-1         , 1
Up Type= 0
Dn Type= 3
Dn Slope=0.01
Boundary for River Rch & Prof#=Elm Creek_2,Reach-1         , 2
Up Type= 0
Dn Type= 3
Dn Slope=0.01
Boundary for River Rch & Prof#=Elm Creek_2,Reach-1         , 3
Up Type= 0
Dn Type= 3
Dn Slope=0.01
Boundary for River Rch & Prof#=Elm Creek_2,Reach-1         , 4
Up Type= 0
Dn Type= 3
Dn Slope=0.01
Boundary for River Rch & Prof#=Elm Creek_2,Reach-1         , 5
Up Type= 0
Dn Type= 3
Dn Slope=0.01
Boundary for River Rch & Prof#=Elm Creek_2,Reach-1         , 6
Up Type= 0
Dn Type= 3
Dn Slope=0.01
Boundary for River Rch & Prof#=Elm Creek_2,Reach-1         , 7
Up Type= 0
Dn Type= 3
Dn Slope=0.01
DSS Import GetInterval= 0
DSS Import GetPeak= 0
DSS Import FillOption= 0

--- Elm Creek_2.g01 (geometry) ---

Geom Title=Existing Conditions
Program Version=4.10

River Reach=Elm Creek_2     ,Reach-1
Reach XY= 30
        1914775.       13940175.      1914869.54     13940077.45
       1914888.4      13939961.7      1915467.14     13939381.17
      1915480.52     13939272.57        1915625.       13939125.
      1915578.08     13939026.58      1915719.53     13938877.45
      1915728.55     13938726.47      1915922.72     13938369.43
      1915821.24     13937926.56       1915676.2      13937664.5
      1915671.25     13937226.55      1915441.71     13936841.63
        1914765.     13936564.37       1914377.3     13936080.83
      1914243.35      13936024.6      1913980.03     13936075.81
      1913793.33     13936025.07      1913680.71     13936073.06
      1913391.28     13935892.14      1913335.44     13935685.94
       1913058.2     13935708.59      1912978.52     13935623.54
      1912975.18     13935493.27      1913121.26     13935223.44
      1913123.03     13935080.68      1912818.83     13934917.14
      1912685.19     13934784.69        1912725.       13934575.

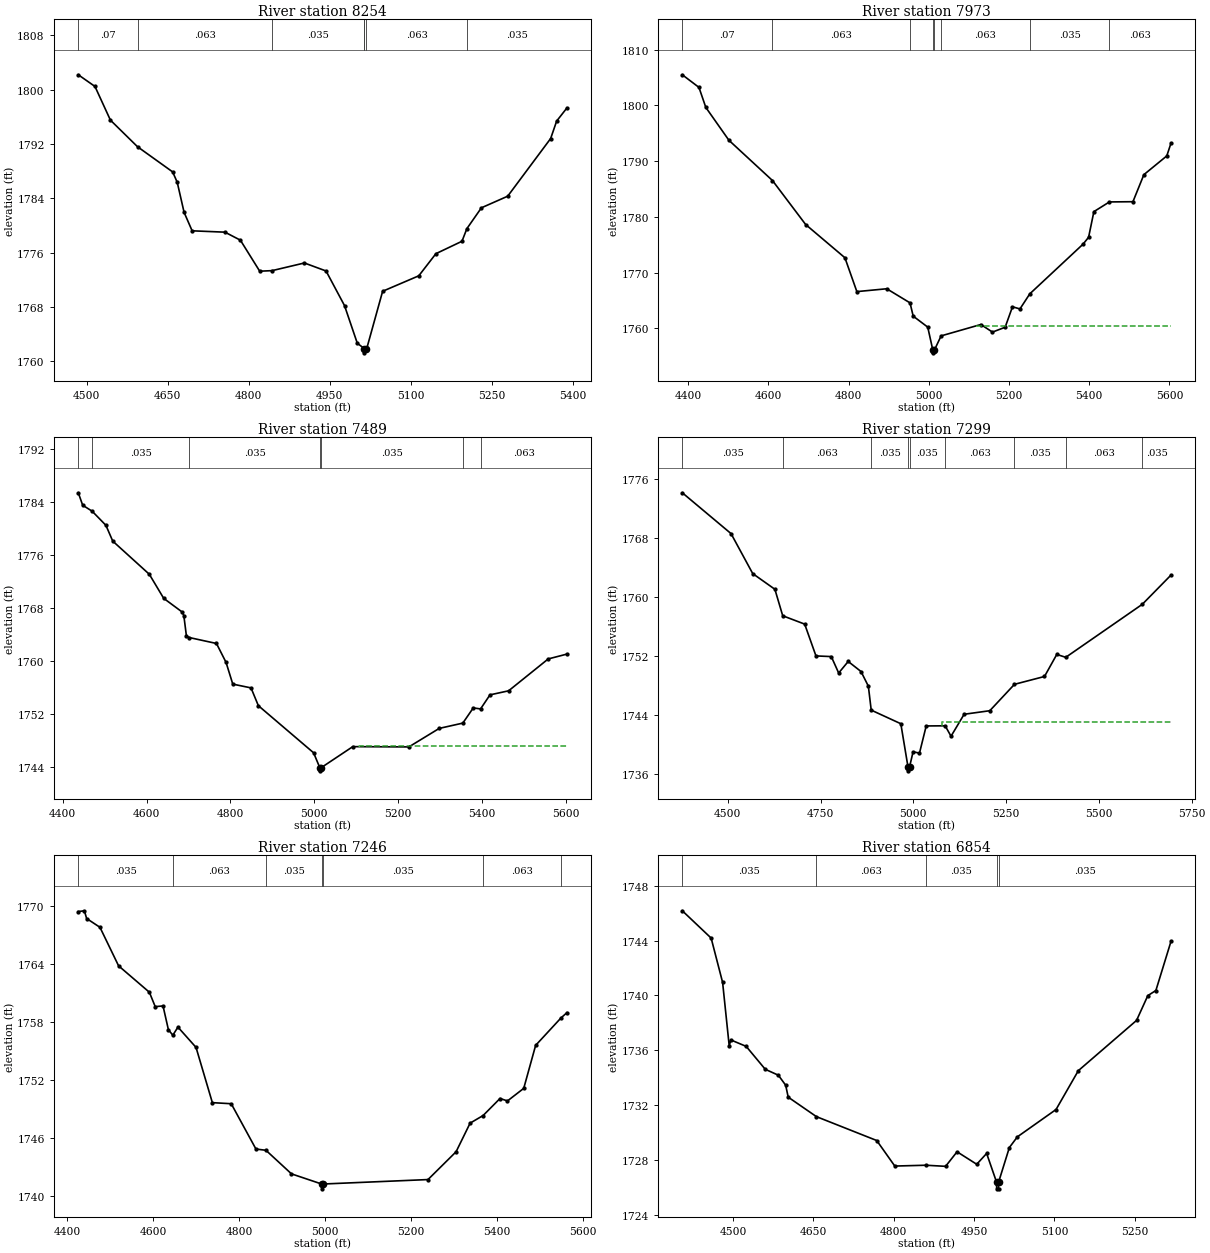
Type RM Length L Ch R = 1 ,8254    ,281,281,281
BEGIN DESCRIPTION:
Elm Creek 2 15.0
END DESCRIPTION:
XS GIS Cut Line= 4
      1915255.49     13940322.25      1914924.33     13939963.42
      1914801.65     13939874.38      1914538.22     13939841.87
#Sta/Elev= 30
  4484.2  1802.2  4515.1 1800.48  4543.7 1795.52  4593.9  1791.6    4659 1787.89
  4667.5 1786.36  4680.2 1781.93  4695.1 1779.21  4755.9 1779.01  4784.5 1777.83
  4820.3 1773.26  4843.1 1773.34  4903.1 1774.47  4943.2 1773.29  4977.4 1768.19
  5001.1 1762.64  5013.4  1761.9  5014.1 1761.73  5014.4 1761.23  5018.1 1761.73
    5048  1770.3    5115 1772.58  5146.7 1775.84    5195 1777.67  5204.1 1779.53
    5231  1782.6  5279.7 1784.31  5359.3 1792.81  5370.4 1795.38  5389.5 1797.32
#Mann= 7 ,-1 , 0
  4484.2     .07       0  4593.9    .063       0  4843.1    .035       0
  5013.4    .063       0  5014.1    .035       0  5018.1    .063       0
  5204.1    .035       0
Bank Sta=5014.1,5018.1
XS Rating Curve= 0 ,0
Exp/Cntr=0.3,0.1

Type RM Length L Ch R = 1 ,7973    ,484,484,484
BEGIN DESCRIPTION:
Elm Creek2 14.0
END DESCRIPTION:
XS GIS Cut Line= 4
      1915502.21     13940214.19      1915114.34     13939758.01
      1915015.83     13939691.64      1914520.38     13939616.39
#Sta/Elev= 30
  4385.1 1805.47  4426.6 1803.21  4443.7 1799.62  4501.4 1793.72  4609.9 1786.51
  4692.7 1778.62  4790.6 1772.66  4820.4 1766.59  4894.9  1767.1    4953 1764.57
  4960.9 1762.19  4997.2 1760.22  5009.8 1756.11    5010 1755.61  5013.8 1756.11
  5030.5 1758.65  5129.6 1760.69  5158.6 1759.33  5190.2  1760.2  5208.5 1763.87
  5227.1 1763.48  5251.7 1766.19  5384.5  1775.1  5398.3 1776.33  5411.5 1780.93
  5450.2 1782.67  5508.9 1782.71  5536.2 1787.56  5593.3 1790.92  5603.8  1793.2
#Mann= 8 ,-1 , 0
  4385.1     .07       0  4609.9    .063       0    4953    .035       0
  5009.8    .035       0  5013.8    .035       0  5030.5    .063       0
  5251.7    .035       0  5450.2    .063       0
#XS Ineff= 2 , 0
                         5116.93         1760.46
Permanent Ineff=
       F       F
Bank Sta=5009.8,5013.8
XS Rating Curve= 0 ,0
Exp/Cntr=0.3,0.1

Type RM Length L Ch R = 1 ,7489    ,190,190,190
BEGIN DESCRIPTION:
Mapping XS 9f7f4e9f
END DESCRIPTION:
XS GIS Cut Line= 4
      1915684.46     13939907.24      1915483.91     13939432.86
      1915328.36     13939330.66      1914865.53     13939291.96
#Sta/Elev= 30
  4437.2 1785.38  4447.7  1783.5  4470.3  1782.6  4503.1 1780.47  4519.4 1778.09
  4606.6 1773.09  4640.9 1769.46  4685.5 1767.37    4689 1766.83  4695.2 1763.74
  4702.3 1763.54  4766.8 1762.65  4789.7 1759.79  4805.7 1756.52  4849.2 1755.95
  4866.7 1753.27  4998.5 1746.16  5013.1 1743.94  5013.3 1743.44  5017.1 1743.94
  5091.9 1747.09  5225.8 1747.05  5298.1 1749.84  5354.4 1750.64  5379.3 1752.93
  5396.7 1752.78  5419.2  1754.9  5463.6 1755.51  5558.1 1760.32  5602.8 1761.05
#Mann= 7 ,-1 , 0
  4437.2     .07       0  4470.3    .035       0  4702.3    .035       0
  5013.1    .035       0  5017.1    .035       0  5354.4    .035       0
  5396.7    .063       0
#XS Ineff= 2 , 0
                         5105.98         1747.24
Permanent Ineff=
       F       F
Bank Sta=5013.1,5017.1
XS Rating Curve= 0 ,0
Exp/Cntr=0.3,0.1

Type RM Length L Ch R = 1 ,7299    ,53,53,53
BEGIN DESCRIPTION:
Elm Creek 2 13.0
END DESCRIPTION:
XS GIS Cut Line= 3
      1915846.05     13939763.35       1915510.5     13939239.78
      1914817.19     13939189.55
#Sta/Elev= 30
  4377.3 1774.08  4508.6 1768.56  4567.1 1763.15  4626.8 1761.03  4647.9 1757.45
  4707.1 1756.32  4737.5 1752.02  4778.8 1751.93  4798.7 1749.71  4824.4 1751.27
  4858.9 1749.91  4878.7 1747.93  4886.4 1744.69  4966.2 1742.85  4985.6 1736.98
  4985.8 1736.48  4989.6 1736.98  4999.2 1739.05  5016.5 1738.88  5034.6 1742.55
  5085.7 1742.57  5101.5 1741.16  5136.8 1744.13    5206 1744.61  5272.5 1748.18
  5353.4 1749.24  5386.5 1752.22  5410.7 1751.83    5617    1759  5694.3 1762.95
#Mann= 9 ,-1 , 0
  4377.3    .035       0  4647.9    .063       0  4886.4    .035       0
  4985.6    .035       0  4989.6    .035       0  5085.7    .063       0
  5272.5    .035       0  5410.7    .063       0    5617    .035       0
#XS Ineff= 2 , 0
                         5076.56         1743.03
Permanent Ineff=
       F       F
Bank Sta=4985.6,4989.6
XS Rating Curve= 0 ,0
Exp/Cntr=0.3,0.1

Type RM Length L Ch R = 1 ,7246    ,392,392,392
BEGIN DESCRIPTION:
Mapping XS 38440874
END DESCRIPTION:
XS GIS Cut Line= 4
      1915838.95     13939692.08      1915596.68     13939243.54
      1915394.65     13939073.49      1915041.38     13938988.53
#Sta/Elev= 30
  4426.1 1769.45  4440.3 1769.53  4445.5 1768.73  4476.5 1767.82  4519.9 1763.83
  4591.5  1761.1  4605.1 1759.61  4623.3 1759.68  4635.8 1757.22  4646.1 1756.65
    4658 1757.49  4700.1 1755.39  4738.1 1749.67    4782 1749.56  4839.5 1744.87
  4862.8 1744.74  4922.2  1742.3  4992.4 1741.25  4992.6 1740.75  4996.4 1741.25
  5239.9 1741.71  5305.3 1744.59  5337.9 1747.55  5368.2 1748.34  5407.5  1750.1
  5424.9 1749.85  5462.7 1751.15  5490.4  1755.6    5549 1758.42  5563.3 1758.99
#Mann= 7 ,-1 , 0
  4426.1    .035       0  4646.1    .063       0  4862.8    .035       0
  4992.4    .035       0  4996.4    .035       0  5368.2    .063       0
    5549    .035       0
Bank Sta=4992.4,4996.4
XS Rating Curve= 0 ,0
Exp/Cntr=0.3,0.1

Type RM Length L Ch R = 1 ,6854    ,488,488,488
BEGIN DESCRIPTION:
Elm Creek 2 12.0
END DESCRIPTION:
XS GIS Cut Line= 3
      1916274.98       13939025.      1915692.13     13938908.52
      1915375.04       13938925.
#Sta/Elev= 30
  4405.6 1746.17  4459.4 1744.18  4480.8 1740.95  4493.1 1736.33  4496.1 1736.76
  4524.8 1736.29  4560.4 1734.62  4584.8 1734.19  4598.5 1733.46  4603.2 1732.59
  4655.9 1731.17  4768.4 1729.43  4802.1 1727.57  4860.1 1727.63  4896.9 1727.55
  4918.3 1728.61    4955  1727.7  4973.5 1728.49  4991.9 1726.41  4992.2 1725.91
  4995.7 1725.91  4995.9 1726.41  5015.9 1728.92  5030.9  1729.7    5103 1731.69
  5144.6 1734.52  5253.2 1738.18  5274.3 1739.99  5289.3 1740.36  5317.5 1743.94
#Mann= 5 ,-1 , 0
  4405.6    .035       0  4655.9    .063       0  4860.1    .035       0
  4991.9    .035       0  4995.9    .035       0
Bank Sta=4991.9,4995.9
XS Rating Curve= 0 ,0
Exp/Cntr=0.3,0.1

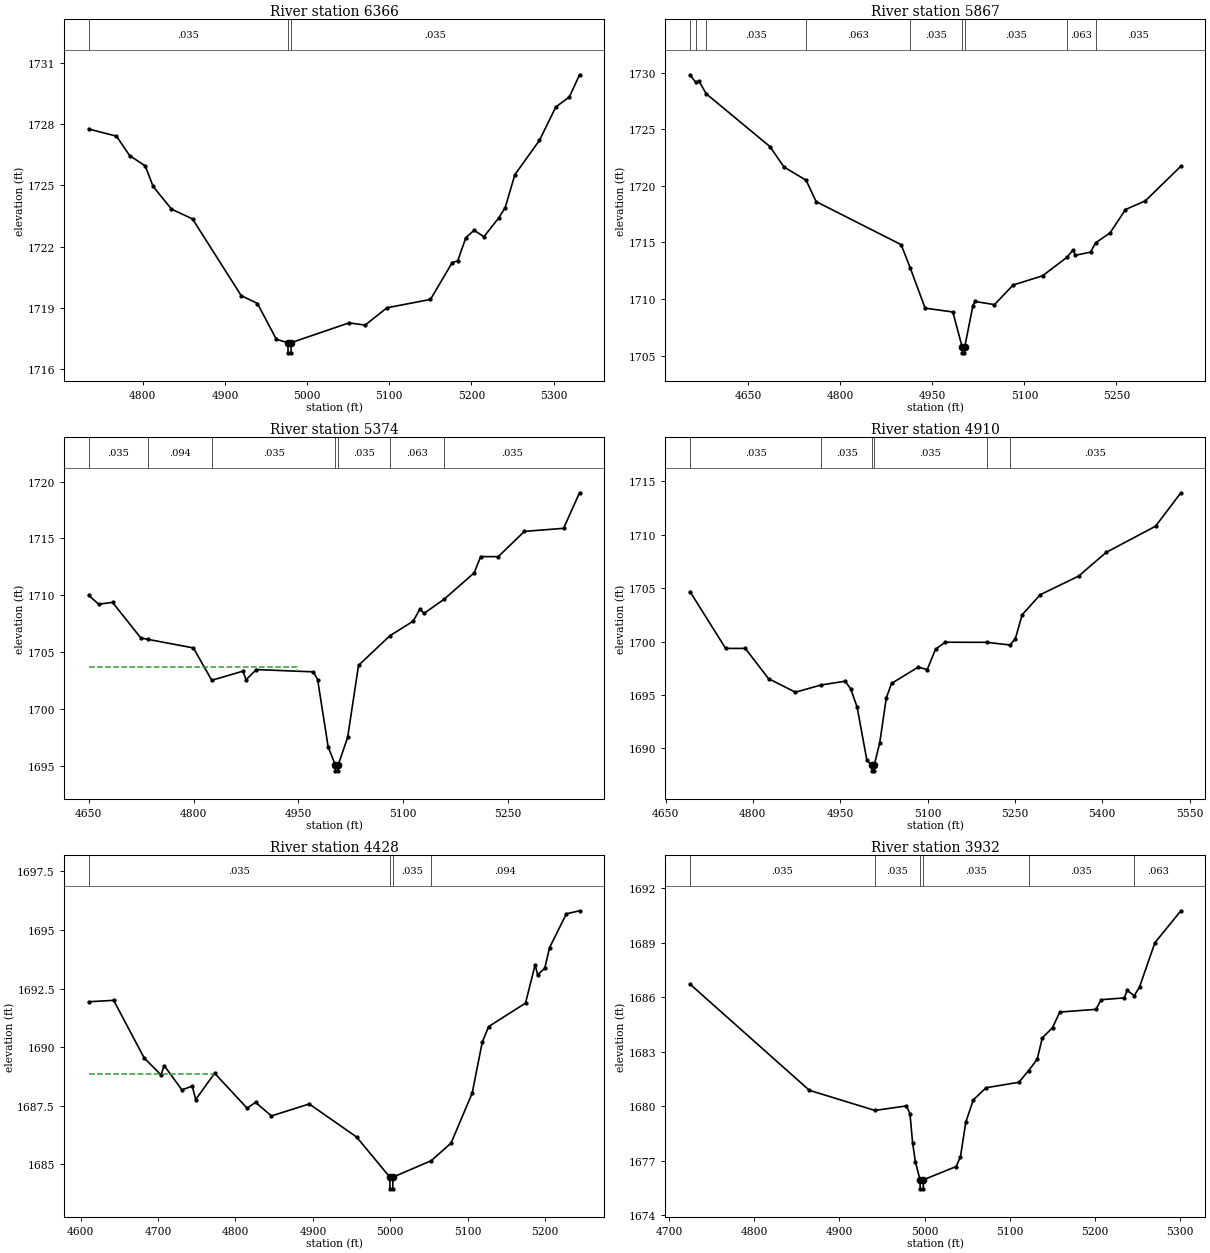
Type RM Length L Ch R = 1 ,6366    ,499,499,499
BEGIN DESCRIPTION:
Elm Creek 2 11.0
END DESCRIPTION:
XS GIS Cut Line= 3
      1916124.99       13938575.      1915875.12     13938484.14
        1915575.       13938625.
#Sta/Elev= 30
  4734.1 1727.77  4767.9 1727.42  4783.9 1726.47    4803 1725.96  4812.6 1724.95
  4834.9 1723.84  4860.5 1723.36  4919.7  1719.6  4939.5 1719.21  4962.6 1717.45
  4976.6 1717.29  4976.8 1716.79  4980.3 1716.79  4980.6 1717.29    5051 1718.26
  5070.6 1718.15  5097.1    1719  5150.1 1719.41  5176.6 1721.22  5183.2  1721.3
  5193.2 1722.44  5203.1  1722.8  5215.2 1722.49    5233  1723.4    5241 1723.91
  5252.8 1725.53  5282.7 1727.21  5302.6 1728.85  5319.1 1729.34  5331.5 1730.43
#Mann= 3 ,-1 , 0
  4734.1    .035       0  4976.6    .035       0  4980.6    .035       0
Bank Sta=4976.6,4980.6
XS Rating Curve= 0 ,0
Exp/Cntr=0.3,0.1

Type RM Length L Ch R = 1 ,5867    ,493,493,493
BEGIN DESCRIPTION:
Elm Creek 2 10.0
END DESCRIPTION:
XS GIS Cut Line= 3
      1916268.24     13938073.82       1915824.6     13938034.26
      1915524.97     13938225.02
#Sta/Elev= 30
  4554.6 1729.81  4563.9 1729.15  4569.6 1729.22  4581.1 1728.13  4685.1 1723.46
  4707.9 1721.66    4744 1720.49  4760.4  1718.6    4899  1714.8  4913.6 1712.77
  4938.1 1709.19  4983.3 1708.85  4998.6 1705.74  4998.8 1705.24  5002.3 1705.24
  5002.6 1705.74  5015.9 1709.38  5019.4 1709.78  5051.2  1709.5  5081.6 1711.23
  5129.7 1712.05  5169.3 1713.68  5179.3 1714.33    5183 1713.86  5207.9 1714.14
  5216.1 1714.96  5239.9 1715.85  5264.8  1717.9  5297.2 1718.67  5355.2 1721.73
#Mann= 9 ,-1 , 0
  4554.6    .035       0  4563.9      .1       0  4581.1    .035       0
    4744    .063       0  4913.6    .035       0  4998.6    .035       0
  5002.6    .035       0  5169.3    .063       0  5216.1    .035       0
#XS Ineff= 2 , 0
                         5019.38         1709.69
Permanent Ineff=
       F       F
Bank Sta=4998.6,5002.6
XS Rating Curve= 0 ,0
Exp/Cntr=0.3,0.1

Type RM Length L Ch R = 1 ,5374    ,464,464,464
BEGIN DESCRIPTION:
Elm Creek 2 9.0
END DESCRIPTION:
XS GIS Cut Line= 3
      1916023.42     13937622.66      1915674.87     13937588.69
      1915336.43     13937686.91
#Sta/Elev= 30
  4649.8 1710.01  4664.1 1709.23    4684 1709.39  4724.4 1706.27  4734.8 1706.14
  4799.7 1705.39    4826 1702.55  4870.7 1703.35  4875.1  1702.6  4889.9 1703.49
  4971.5 1703.29  4977.6 1702.59  4992.6 1696.71  5002.9  1695.1  5003.1  1694.6
  5006.6  1694.6  5006.9  1695.1  5020.5 1697.54  5036.1 1703.86    5081 1706.46
  5114.3 1707.74  5123.9  1708.8  5129.8 1708.42  5158.9 1709.68  5201.6 1711.98
  5210.9 1713.41    5236  1713.4  5273.5 1715.62  5329.6 1715.89  5352.4 1719.01
#Mann= 7 ,-1 , 0
  4649.8    .035       0  4734.8    .094       0    4826    .035       0
  5002.9    .035       0  5006.9    .035       0    5081    .063       0
  5158.9    .035       0
#XS Ineff= 2 , 0
         4948.45 1703.71
Permanent Ineff=
       F       F
Bank Sta=5002.9,5006.9
XS Rating Curve= 0 ,0
Exp/Cntr=0.3,0.1

Type RM Length L Ch R = 1 ,4910    ,482,482,482
BEGIN DESCRIPTION:
Elm Creek 2 8.0
END DESCRIPTION:
XS GIS Cut Line= 3
      1915925.04     13937074.99      1915624.06     13937140.39
      1915210.56     13937480.02
#Sta/Elev= 30
    4692 1704.68  4753.2 1699.36    4787 1699.36  4826.9 1696.53    4873 1695.26
  4917.4 1695.94  4958.4 1696.29  4968.1 1695.57    4979 1693.87  4995.8  1688.9
  5004.3  1688.4  5004.5  1687.9    5008  1687.9  5008.3  1688.4  5017.9 1690.53
  5029.1 1694.71  5038.1 1696.08  5083.9 1697.61  5099.5 1697.38  5113.7 1699.29
  5130.5 1699.94  5201.6 1699.93  5241.6 1699.68  5250.8 1700.27  5262.5 1702.51
  5293.6 1704.39  5359.5 1706.13  5406.8 1708.35  5491.6  1710.8  5535.1 1713.93
#Mann= 6 ,-1 , 0
    4692    .035       0  4917.4    .035       0  5004.3    .035       0
  5008.3    .035       0  5201.6    .063       0  5241.6    .035       0
Bank Sta=5004.3,5008.3
XS Rating Curve= 0 ,0
Exp/Cntr=0.3,0.1

Type RM Length L Ch R = 1 ,4428    ,496,496,496
BEGIN DESCRIPTION:
Elm Creek 2 7.0
END DESCRIPTION:
XS GIS Cut Line= 3
      1915625.02     13936524.98      1915338.16     13936788.75
      1915275.01     13937024.96
#Sta/Elev= 30
  4610.3 1691.94  4642.6    1692  4682.1 1689.54  4703.8 1688.82  4707.9 1689.22
  4730.8 1688.18  4744.1 1688.34  4748.6 1687.77  4773.1 1688.89    4815  1687.4
    4826 1687.65  4846.4 1687.07  4895.3 1687.58  4956.5 1686.17  4999.4 1684.46
  4999.7 1683.96  5003.2 1683.96  5003.4 1684.46  5052.9 1685.16  5078.5 1685.91
  5105.8 1688.04  5118.8 1690.21    5127 1690.88  5174.7 1691.88  5187.2 1693.52
  5190.3 1693.09  5199.6 1693.37  5205.8 1694.25  5227.5 1695.69  5244.5 1695.82
#Mann= 4 ,-1 , 0
  4610.3    .035       0  4999.4    .035       0  5003.4    .035       0
  5052.9    .094       0
#XS Ineff= 2 , 0
         4770.63 1688.87
Permanent Ineff=
       F       F
Bank Sta=4999.4,5003.4
XS Rating Curve= 0 ,0
Exp/Cntr=0.3,0.1

Type RM Length L Ch R = 1 ,3932    ,493,493,493
BEGIN DESCRIPTION:
Elm Creek 2 6.0
END DESCRIPTION:
XS GIS Cut Line= 3
      1915125.01     13936474.99      1914893.43      13936624.4
        1914875.     13936925.04
#Sta/Elev= 30
  4724.4 1686.72  4864.6 1680.87  4941.7 1679.76  4978.8 1680.01  4982.9 1679.57
    4986 1677.97  4989.2 1676.94  4994.7 1675.94  4994.9 1675.44  4998.4 1675.44
  4998.7 1675.94  5037.2 1676.67  5042.2 1677.21  5048.5 1679.12  5057.3 1680.34
  5072.3 1681.01  5110.8 1681.31  5122.4 1681.96  5132.4 1682.58  5138.4 1683.76
  5150.4 1684.32  5158.9 1685.18  5201.5 1685.33  5207.5 1685.86  5234.6 1685.96
  5238.2 1686.37  5246.4 1686.08  5252.6 1686.56  5270.7    1689  5301.2 1690.76
#Mann= 6 ,-1 , 0
  4724.4    .035       0  4941.7    .035       0  4994.7    .035       0
  4998.7    .035       0  5122.4    .035       0  5246.4    .063       0
Bank Sta=4994.7,4998.7
XS Rating Curve= 0 ,0
Exp/Cntr=0.3,0.1

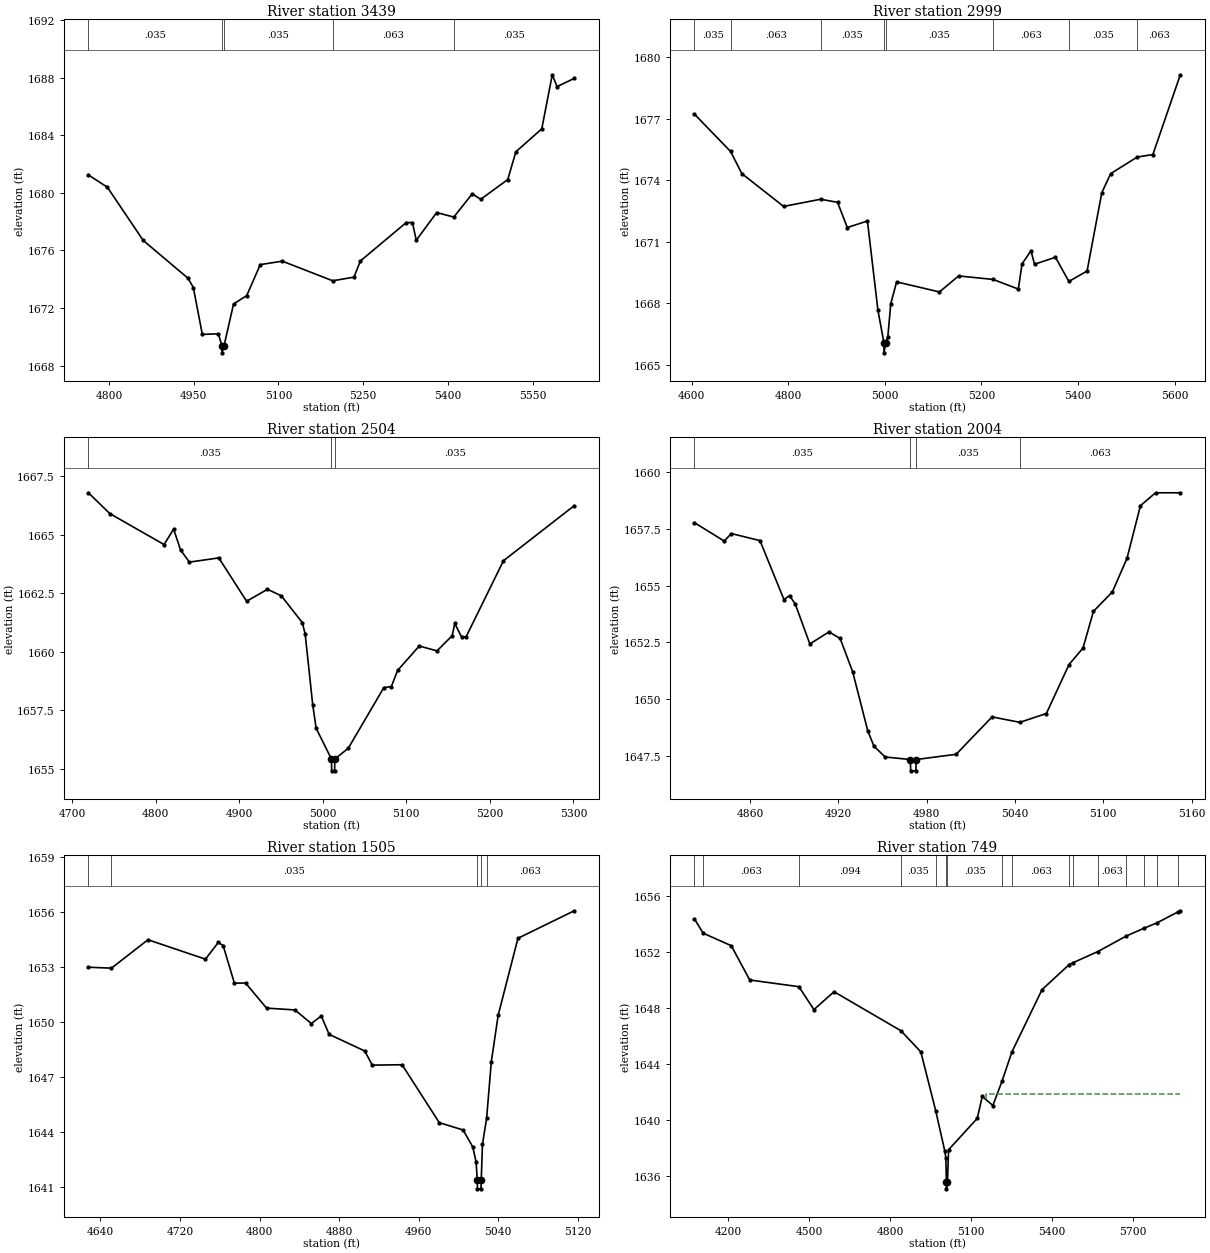
Type RM Length L Ch R = 1 ,3439    ,440,440,440
BEGIN DESCRIPTION:
Elm Creek 2 5.0
END DESCRIPTION:
XS GIS Cut Line= 3
      1914774.98     13936225.01       1914551.3     13936301.82
        1914525.     13936924.97
#Sta/Elev= 30
  4763.5 1681.24  4797.1 1680.39  4860.5  1676.7    4940 1674.07  4949.3 1673.43
  4965.2 1670.18  4993.7 1670.22  4999.7  1669.4    5000  1668.9  5003.7  1669.4
  5020.5 1672.29  5043.8 1672.87  5067.8 1675.02  5106.8 1675.26    5196  1673.9
  5233.7 1674.15    5245 1675.27    5326 1677.93  5337.2 1677.94    5344 1676.71
  5380.1 1678.63  5410.5 1678.32  5443.1 1679.93  5458.1 1679.55  5505.9 1680.92
  5520.4 1682.85  5566.2 1684.44  5584.8 1688.19  5593.3 1687.37  5623.7 1687.94
#Mann= 5 ,-1 , 0
  4763.5    .035       0  4999.7    .035       0  5003.7    .035       0
    5196    .063       0  5410.5    .035       0
#XS Ineff= 2 , 0
                         5133.47         1674.73
Permanent Ineff=
       F       F
Bank Sta=4999.7,5003.7
XS Rating Curve= 0 ,0
Exp/Cntr=0.3,0.1

Type RM Length L Ch R = 1 ,2999    ,495,495,495
BEGIN DESCRIPTION:
Elm Creek 2 4.0
END DESCRIPTION:
XS GIS Cut Line= 3
      1914624.96     13935925.01      1914243.35      13936024.6
      1914124.99     13936625.05
#Sta/Elev= 30
  4605.6 1677.23  4680.4 1675.41  4703.8 1674.33  4790.3 1672.73  4866.9 1673.08
    4902 1672.93  4922.2  1671.7  4963.9 1672.02  4985.7 1667.66    4998 1666.09
  4998.2 1665.59    5002 1666.09  5006.1 1666.36  5012.2 1667.98  5024.4 1669.05
  5113.1 1668.56  5152.8 1669.34  5224.1 1669.17  5276.5  1668.7  5284.1 1669.92
  5302.7 1670.57    5310 1669.91  5353.4 1670.25  5381.2 1669.07  5418.9 1669.58
  5449.4  1673.4  5467.8 1674.33  5522.9 1675.14  5555.2 1675.26    5612 1679.15
#Mann= 8 ,-1 , 0
  4605.6    .035       0  4680.4    .063       0  4866.9    .035       0
    4998    .035       0    5002    .035       0  5224.1    .063       0
  5381.2    .035       0  5522.9    .063       0
Bank Sta=4998,5002
XS Rating Curve= 0 ,0
Exp/Cntr=0.3,0.1

Type RM Length L Ch R = 1 ,2504    ,500,500,500
BEGIN DESCRIPTION:
Elm Creek 2 3.0
END DESCRIPTION:
XS GIS Cut Line= 3
        1913975.       13935825.      1913780.56     13936027.31
        1913825.     13936325.01
#Sta/Elev= 30
  4719.4 1666.79  4745.1  1665.9    4810 1664.58  4821.4 1665.24  4829.7 1664.35
  4840.3 1663.83  4875.5 1664.01  4908.8 1662.16  4933.8 1662.67  4950.4 1662.39
  4975.4 1661.25  4978.9 1660.76  4987.9 1657.75    4992 1656.74  5010.4 1655.42
  5010.6 1654.92  5014.1 1654.92  5014.4 1655.42  5030.6 1655.89    5073 1658.47
  5082.1 1658.52  5089.6 1659.21  5115.5 1660.25  5136.7 1660.04  5154.9 1660.69
    5158 1661.21  5166.2 1660.63  5171.5 1660.64  5216.3 1663.89    5301 1666.24
#Mann= 3 ,-1 , 0
  4719.4    .035       0  5010.4    .035       0  5014.4    .035       0
Bank Sta=5010.4,5014.4
XS Rating Curve= 0 ,0
Exp/Cntr=0.3,0.1

Type RM Length L Ch R = 1 ,2004    ,499,499,499
BEGIN DESCRIPTION:
Elm Creek 2 2.0
END DESCRIPTION:
XS GIS Cut Line= 3
      1913524.97     13935775.03      1913385.35     13935885.12
      1913325.02     13936024.96
#Sta/Elev= 30
  4822.2 1657.78  4842.4 1656.97  4847.3  1657.3  4866.7 1656.99    4883 1654.39
  4886.8 1654.56  4890.7 1654.19  4900.6 1652.43  4913.6 1652.96  4921.2 1652.67
  4929.7  1651.2  4939.9 1648.61  4944.1 1647.92  4951.8 1647.44  4968.9 1647.33
  4969.1 1646.83  4972.6 1646.83  4972.9 1647.33    5000 1647.56  5024.4 1649.21
  5043.3 1648.97  5061.3 1649.36  5076.7 1651.52  5086.2 1652.25  5093.3 1653.87
  5106.1 1654.72  5116.1 1656.21  5125.2 1658.53  5135.5  1659.1  5152.3  1659.1
#Mann= 4 ,-1 , 0
  4822.2    .035       0  4968.9    .035       0  4972.9    .035       0
  5043.3    .063       0
Bank Sta=4968.9,4972.9
XS Rating Curve= 0 ,0
Exp/Cntr=0.3,0.1

Type RM Length L Ch R = 1 ,1505    ,756,756,756
BEGIN DESCRIPTION:
Elm Creek 2 1.0
END DESCRIPTION:
XS GIS Cut Line= 3
      1913366.73     13935494.28      1913068.79      13935717.2
      1913024.98     13935825.04
#Sta/Elev= 30
  4627.9 1652.98  4651.1 1652.93  4687.8 1654.48  4745.6 1653.42  4758.5 1654.33
  4763.4 1654.16  4774.7 1652.11  4785.9 1652.12    4807 1650.75  4835.6 1650.65
    4852 1649.91  4862.1 1650.32  4869.9 1649.32  4905.8 1648.41  4913.3 1647.64
  4943.3 1647.66  4980.7  1644.5  5004.7  1644.1  5014.4 1643.17  5017.7 1642.36
  5018.9 1641.39  5019.1 1640.89  5022.6 1640.89  5022.9 1641.39  5024.1 1643.31
  5028.3 1644.74    5033 1647.82  5039.9 1650.36  5059.8 1654.56  5116.4 1656.06
#Mann= 5 ,-1 , 0
  4627.9    .063       0  4651.1    .035       0  5018.9    .035       0
  5022.9    .035       0  5028.3    .063       0
Bank Sta=5018.9,5022.9
XS Rating Curve= 0 ,0
Exp/Cntr=0.3,0.1

Type RM Length L Ch R = 1 ,749     ,0,0,0
BEGIN DESCRIPTION:
Elm Creek2 0.0
END DESCRIPTION:
XS GIS Cut Line= 4
      1913982.84      13935030.9      1913270.65     13934932.02
       1912952.2      13935162.8      1912675.12     13935790.89
#Sta/Elev= 30
  4075.1 1654.39  4107.1 1653.37  4211.6 1652.47  4279.7 1650.02  4461.7 1649.54
  4517.4  1647.9  4591.9 1649.18  4839.5 1646.39  4913.2 1644.88  4968.4 1640.66
  5002.1 1637.77  5005.9 1637.28  5007.8 1635.58    5008 1635.08  5011.8 1635.58
  5016.1 1637.88  5122.2 1640.12  5140.7 1641.69    5180 1641.04    5214 1642.79
  5250.4 1644.87    5362 1649.33  5462.4 1651.12  5477.3 1651.26  5568.4 1652.05
  5674.4 1653.17  5740.7 1653.73  5787.8 1654.11  5866.6  1654.9  5873.9 1654.97
#Mann= 16 ,-1 , 0
  4075.1    .094       0  4107.1    .063       0  4461.7    .094       0
  4839.5    .035       0  4968.4    .035       0  5007.8    .035       0
  5011.8    .035       0    5214    .035       0  5250.4    .063       0
  5462.4    .035       0  5477.3     .12       0  5568.4    .063       0
  5674.4     .12       0  5740.7    .063       0  5787.8    .035       0
  5866.6    .063       0
#XS Ineff= 2 , 0
                         5152.85         1641.83
Permanent Ineff=
       F       F
Bank Sta=5007.8,5011.8
XS Rating Curve= 0 ,0
Exp/Cntr=0.3,0.1

Chan Stop Cuts=-1
Use User Specified Reach Order=0
Composite Channel Slope=5