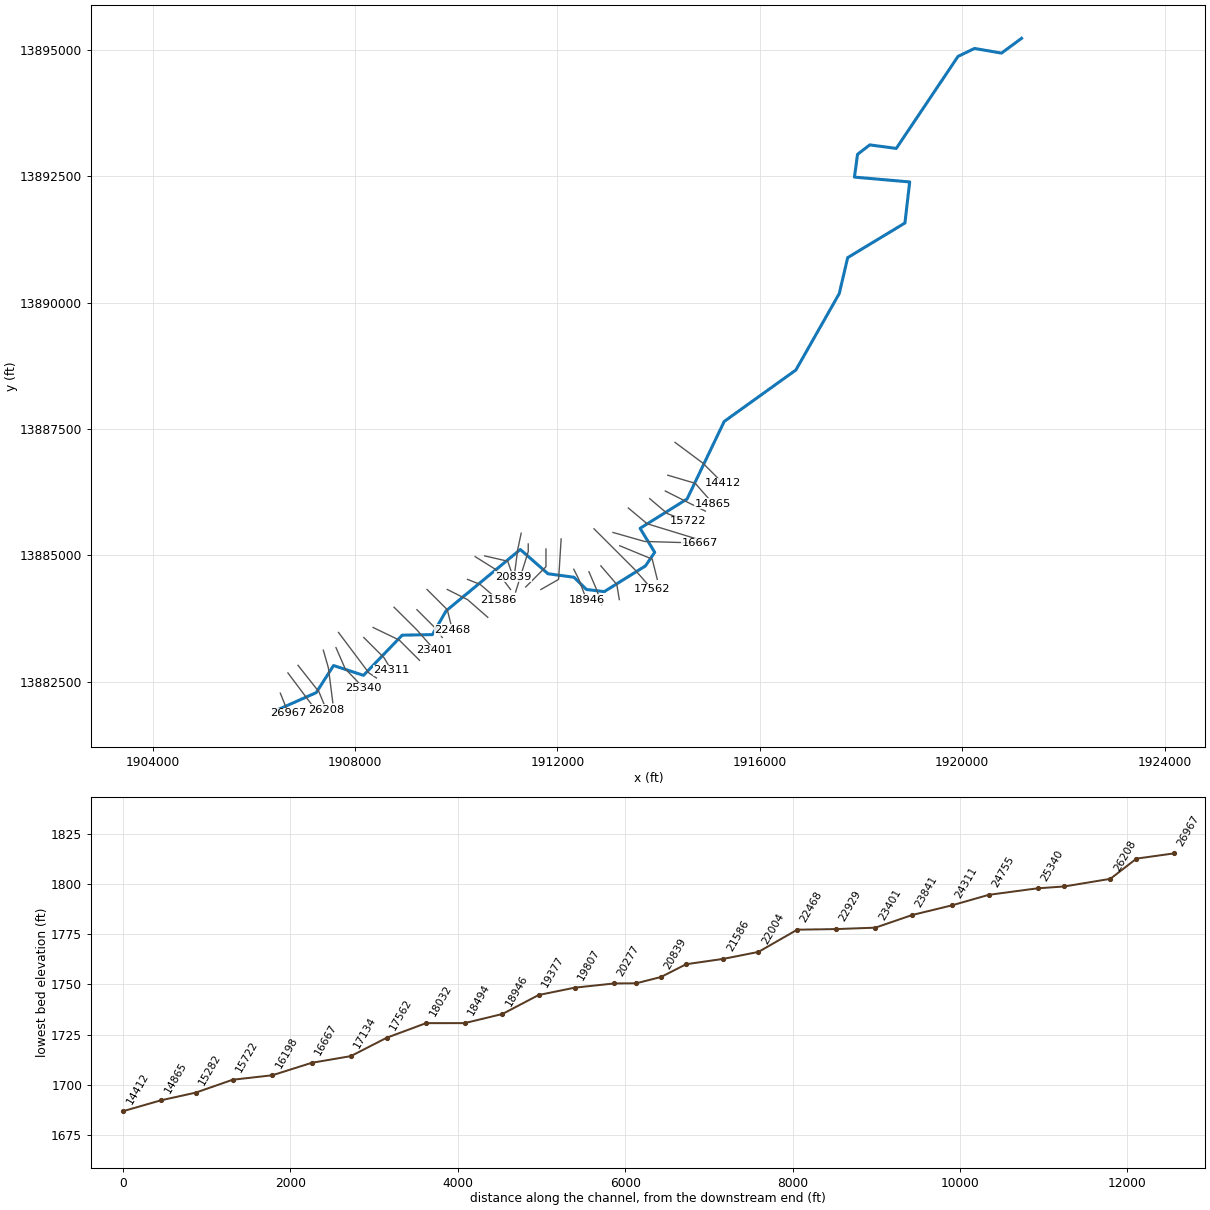
--- Fall Creek.prj (project) ---

Proj Title=Fall Creek Base Level Engineering
Current Plan=p01
Default Exp/Contr=0.3,0.1
English Units
Geom File=g01
Flow File=f01
Plan File=p01
BEGIN DESCRIPTION:
Fall Creek
END DESCRIPTION:

--- Fall Creek.p01 (plan) ---

Plan Title=Multiple Run
Short Identifier=Multiple
Geom File=g01
Flow File=f01
Subcritical Flow
K Sum by GR= 0
Std Step Tol= 0.01
Critical Tol= 0.01
Num of Std Step Trials= 20
Max Error Tol= 0.3
Flow Tol Ratio= 0.001
Split Flow NTrial= 30
Split Flow Tol= 0.02
Split Flow Ratio= 0.02
Log Output Level= 0
Friction Slope Method= 1
Unsteady Friction Slope Method= 2
Unsteady Bridges Friction Slope Method= 1
Parabolic Critical Depth
Global Vel Dist=  1 , 1 , 1
Global Log Level= 0
CheckData=True
Encroach Param= -1, 0, 0, 0
BEGIN DESCRIPTION:
Multiple Run
END DESCRIPTION:

--- Fall Creek.f01 (steady flow) ---

Flow Title=Multiple
Number of Profiles=7
Profile Names=10-year,25-year,50-year,1pct_min,100-year,1pct_plu,500-year
River Rch & RM= Fall Creek,Reach-1,26967
    2435    4298    6134    4223    8425   16811   15703
River Rch & RM= Fall Creek,Reach-1,20545
    2840    5049    7238    5003    9982   19916   18756
River Rch & RM= Fall Creek,Reach-1,18494
    3521    6320    9120    6339   12648   25236   24041
River Rch & RM= Fall Creek,Reach-1,15722
    3816    6892    9984    6963   13894   27722   26605
River Rch & RM= Fall Creek,Reach-1,13072
    4453    8100   11789    8258   16477   32876   31826
River Rch & RM= Fall Creek,Reach-1,12192
    4899    8930   13016    9126   18208   36330   35239
River Rch & RM= Fall Creek,Reach-1,8171
    5025    9155   13338    9347   18649   37209   36051
River Rch & RM= Fall Creek,Reach-1,4984
    5228    9531   13891    9735   19425   38758   37562
River Rch & RM= Fall Creek,Reach-1,2787
    5325    9706   14145    9911   19775   39457   38223
Boundary for River Rch & Prof#=Fall Creek,Reach-1,1
Up Type=0
Dn Type=3
Dn Slope=0.005
Boundary for River Rch & Prof#=Fall Creek,Reach-1,2
Up Type=0
Dn Type=3
Dn Slope=0.005
Boundary for River Rch & Prof#=Fall Creek,Reach-1,3
Up Type=0
Dn Type=3
Dn Slope=0.005
Boundary for River Rch & Prof#=Fall Creek,Reach-1,4
Up Type=0
Dn Type=3
Dn Slope=0.005
Boundary for River Rch & Prof#=Fall Creek,Reach-1,5
Up Type=0
Dn Type=3
Dn Slope=0.005
Boundary for River Rch & Prof#=Fall Creek,Reach-1,6
Up Type=0
Dn Type=3
Dn Slope=0.005
Boundary for River Rch & Prof#=Fall Creek,Reach-1,7
Up Type=0
Dn Type=3
Dn Slope=0.005

--- Fall Creek.g01 (geometry) ---

Geom Title=Existing Conditions

River Reach=Fall Creek,Reach-1
Reach XY= 30
      1906425.00     13881925.00      1907234.85     13882285.48
      1907576.55     13882821.25      1908168.89     13882626.79
      1908933.48     13883421.49      1909531.19     13883432.75
      1909801.16     13883902.15      1911268.42     13885115.73
      1911814.63     13884636.09      1912328.32     13884566.96
      1912575.00     13884325.00      1912928.32     13884283.04
      1913741.76     13884791.43      1913924.64     13885059.73
      1913635.18     13885534.71      1914564.22     13886115.32
      1915298.01     13887648.47      1916714.24     13888665.32
      1917571.39     13890176.50      1917738.61     13890888.24
      1918869.48     13891572.57      1918963.77     13892385.03
      1917872.28     13892480.38      1917933.14     13892931.06
      1918175.09     13893117.72      1918698.47     13893048.01
      1919918.55     13894867.26      1920245.06     13895025.21
      1920778.41     13894932.81      1921175.00     13895225.00

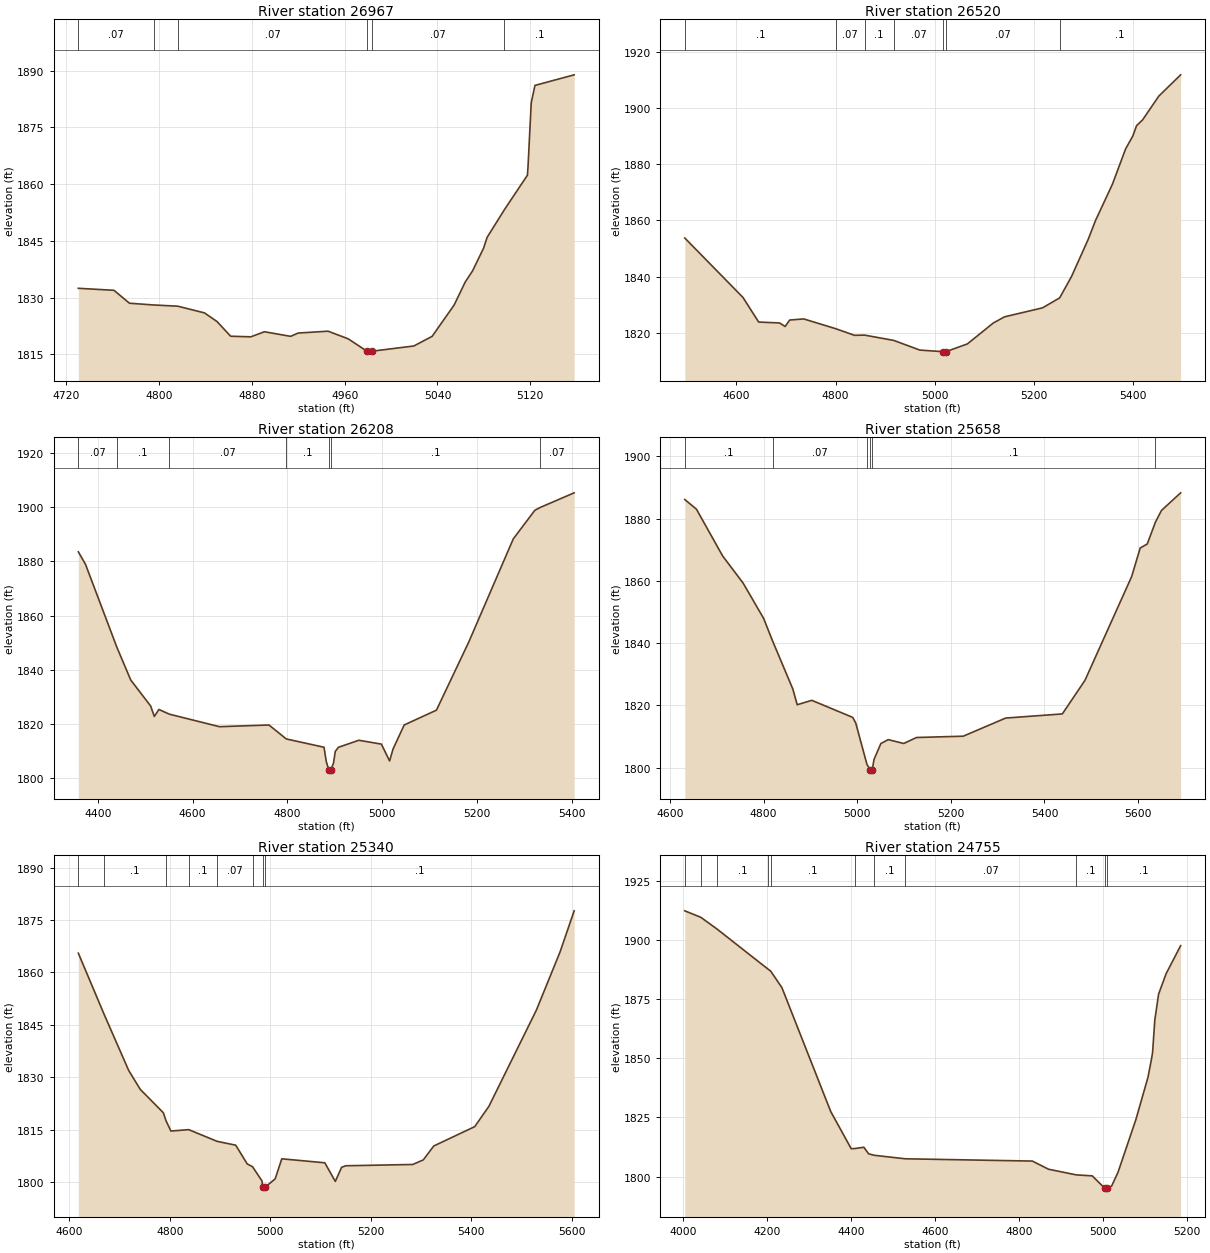
Type RM Length L Ch R = 1,26967,447,447,447
BEGIN DESCRIPTION:
Fall Creek 53.0
END DESCRIPTION:
XS GIS Cut Line= 3
      1906525.00     13882275.01      1906625.00     13882025.00
      1906675.01     13881874.98
#Sta/Elev= 30
  4730.4 1832.47  4761.1 1831.94  4774.5 1828.52  4795.4 1828.06  4816.1 1827.74
  4839.1 1825.97  4850.0 1823.67  4861.7 1819.80  4879.1 1819.64  4890.8 1820.98
  4913.4 1819.77  4919.9 1820.64  4945.7 1821.13  4963.1 1819.10  4979.2 1815.83
  4979.5 1815.33  4983.3 1815.83  5019.6 1817.22  5035.4 1819.77  5054.4 1828.08
  5063.9 1834.13  5070.2 1837.06  5079.7 1843.06  5082.8 1845.96  5097.7 1853.26
  5117.5 1862.36  5118.0 1864.47  5120.8 1881.49  5124.0 1886.11  5157.8 1888.91
#Mann=6,-1,0
  4730.4    0.07       0  4795.4     0.1       0  4816.1    0.07       0
  4979.2    0.05       0  4983.3    0.07       0  5097.7     0.1       0
Bank Sta=4979.2,4983.3
Exp/Cntr=0.3,0.1

Type RM Length L Ch R = 1,26520,312,312,312
BEGIN DESCRIPTION:
Fall Creek 52.0
END DESCRIPTION:
XS GIS Cut Line= 3
      1906675.02     13882674.97      1906975.00     13882275.00
      1907275.02     13881874.97
#Sta/Elev= 30
  4496.0 1853.73  4613.3 1832.57  4645.0 1823.79  4687.1 1823.48  4698.4 1822.22
  4707.6 1824.52  4735.9 1824.91  4800.6 1821.42  4838.3 1819.07  4858.9 1819.14
  4917.4 1817.26  4970.0 1813.82  5017.7 1813.23  5018.0 1812.73  5022.3 1813.23
  5065.9 1816.01  5118.4 1823.48  5140.9 1825.66  5217.6 1828.86  5252.0 1832.40
  5275.9 1839.99  5309.6 1853.25  5324.6 1860.06  5358.4 1872.87  5385.0 1885.45
  5399.6 1890.06  5407.1 1893.74  5419.1 1895.76  5452.1 1904.29  5496.0 1911.85
#Mann=7,-1,0
  4496.0     0.1       0  4800.6    0.07       0  4858.9     0.1       0
  4917.4    0.07       0  5017.7    0.05       0  5022.3    0.07       0
  5252.0     0.1       0
Bank Sta=5017.7,5022.3
Exp/Cntr=0.3,0.1

Type RM Length L Ch R = 1,26208,550,550,550
BEGIN DESCRIPTION:
Fall Creek 51.0
END DESCRIPTION:
XS GIS Cut Line= 3
      1906874.98     13882825.02      1907288.76     13882300.76
      1907433.53     13881950.37
#Sta/Elev= 30
  4358.6 1883.53  4373.7 1878.95  4439.9 1848.38  4469.3 1836.25  4511.4 1826.65
  4519.0 1822.83  4528.8 1825.39  4550.9 1823.65  4656.6 1819.04  4761.2 1819.66
  4797.7 1814.52  4877.4 1811.46  4882.1 1806.24  4887.4 1803.15  4887.7 1802.65
  4892.0 1803.15  4897.4 1805.59  4901.2 1809.93  4907.8 1811.44  4950.9 1814.03
  4998.5 1812.62  5015.9 1806.40  5023.1 1810.78  5046.7 1819.67  5114.8 1825.14
  5183.0 1850.24  5277.1 1888.31  5322.6 1898.85  5334.0 1899.90  5405.6 1905.29
#Mann=7,-1,0
  4358.6    0.07       0  4439.9     0.1       0  4550.9    0.07       0
  4797.7     0.1       0  4887.4    0.05       0  4892.0     0.1       0
  5334.0    0.07       0
Bank Sta=4887.4,4892
Exp/Cntr=0.3,0.1

Type RM Length L Ch R = 1,25658,318,318,318
BEGIN DESCRIPTION:
Fall Creek 50.0
END DESCRIPTION:
XS GIS Cut Line= 3
      1907375.00     13883124.99      1907475.00     13882775.00
      1907562.88     13882085.37
#Sta/Elev= 30
  4631.7 1886.16  4656.6 1883.05  4712.7 1867.98  4756.4 1859.27  4800.1 1847.94
  4819.3 1840.67  4862.5 1825.24  4871.8 1820.18  4903.0 1821.60  4990.4 1816.12
  4996.9 1814.29  5020.9 1800.98  5027.5 1799.34  5027.9 1798.84  5032.2 1799.34
  5035.9 1802.58  5050.5 1807.70  5066.2 1808.97  5099.4 1807.73  5126.7 1809.65
  5226.5 1810.07  5317.2 1815.90  5438.2 1817.23  5486.5 1828.01  5586.3 1861.38
  5604.5 1870.56  5619.6 1871.86  5637.1 1878.89  5649.9 1882.63  5690.9 1888.31
#Mann=6,-1,0
  4631.7     0.1       0  4819.3    0.07       0  5020.9     0.1       0
  5027.5    0.05       0  5032.2     0.1       0  5637.1    0.07       0
Bank Sta=5027.5,5032.2
Exp/Cntr=0.3,0.1

Type RM Length L Ch R = 1,25340,585,585,585
BEGIN DESCRIPTION:
Fall Creek 49.0
END DESCRIPTION:
XS GIS Cut Line= 3
      1907625.00     13883175.01      1907807.98     13882755.83
      1908175.02     13882374.98
#Sta/Elev= 30
  4618.2 1865.49  4669.3 1848.04  4718.5 1831.88  4741.4 1826.49  4787.2 1819.82
  4792.7 1817.50  4802.3 1814.56  4837.8 1814.96  4894.1 1811.62  4931.3 1810.51
  4954.2 1805.14  4964.7 1804.35  4983.6 1800.26  4984.7 1798.43  4985.1 1797.93
  4989.4 1798.43  5009.8 1800.88  5022.9 1806.61  5108.5 1805.47  5129.4 1800.14
  5141.9 1804.18  5150.2 1804.62  5283.5 1804.99  5304.4 1806.30  5325.2 1810.28
  5406.7 1815.82  5435.0 1821.66  5529.4 1849.19  5576.4 1865.82  5604.5 1877.61
#Mann=8,-1,0
  4618.2    0.07       0  4669.3     0.1       0  4792.7    0.07       0
  4837.8     0.1       0  4894.1    0.07       0  4964.7     0.1       0
  4984.7    0.05       0  4989.4     0.1       0
Bank Sta=4984.7,4989.4
Exp/Cntr=0.3,0.1

Type RM Length L Ch R = 1,24755,444,444,444
BEGIN DESCRIPTION:
Fall Creek 48.0
END DESCRIPTION:
XS GIS Cut Line= 3
      1907674.98     13883475.03      1908275.00     13882675.00
      1908424.99     13882575.01
#Sta/Elev= 30
  4004.3 1912.53  4042.3 1909.80  4081.2 1904.79  4201.3 1888.00  4208.6 1887.04
  4235.5 1879.99  4351.7 1827.52  4400.5 1811.77  4409.0 1811.85  4430.5 1812.40
  4441.8 1809.64  4455.1 1809.00  4528.7 1807.51  4831.7 1806.54  4870.3 1803.08
  4936.6 1800.68  4974.2 1800.28  5003.4 1795.16  5003.8 1794.66  5008.6 1795.16
  5020.4 1795.97  5035.6 1801.81  5078.1 1824.12  5106.9 1842.03  5115.6 1850.09
  5117.8 1852.46  5123.2 1866.36  5132.2 1877.28  5150.2 1885.95  5184.6 1897.76
#Mann=11,-1,0
  4004.3     0.1       0  4042.3    0.07       0  4081.2     0.1       0
  4201.3    0.07       0  4208.6     0.1       0  4409.0    0.07       0
  4455.1     0.1       0  4528.7    0.07       0  4936.6     0.1       0
  5003.4    0.05       0  5008.6     0.1       0
Bank Sta=5003.4,5008.6
Exp/Cntr=0.3,0.1

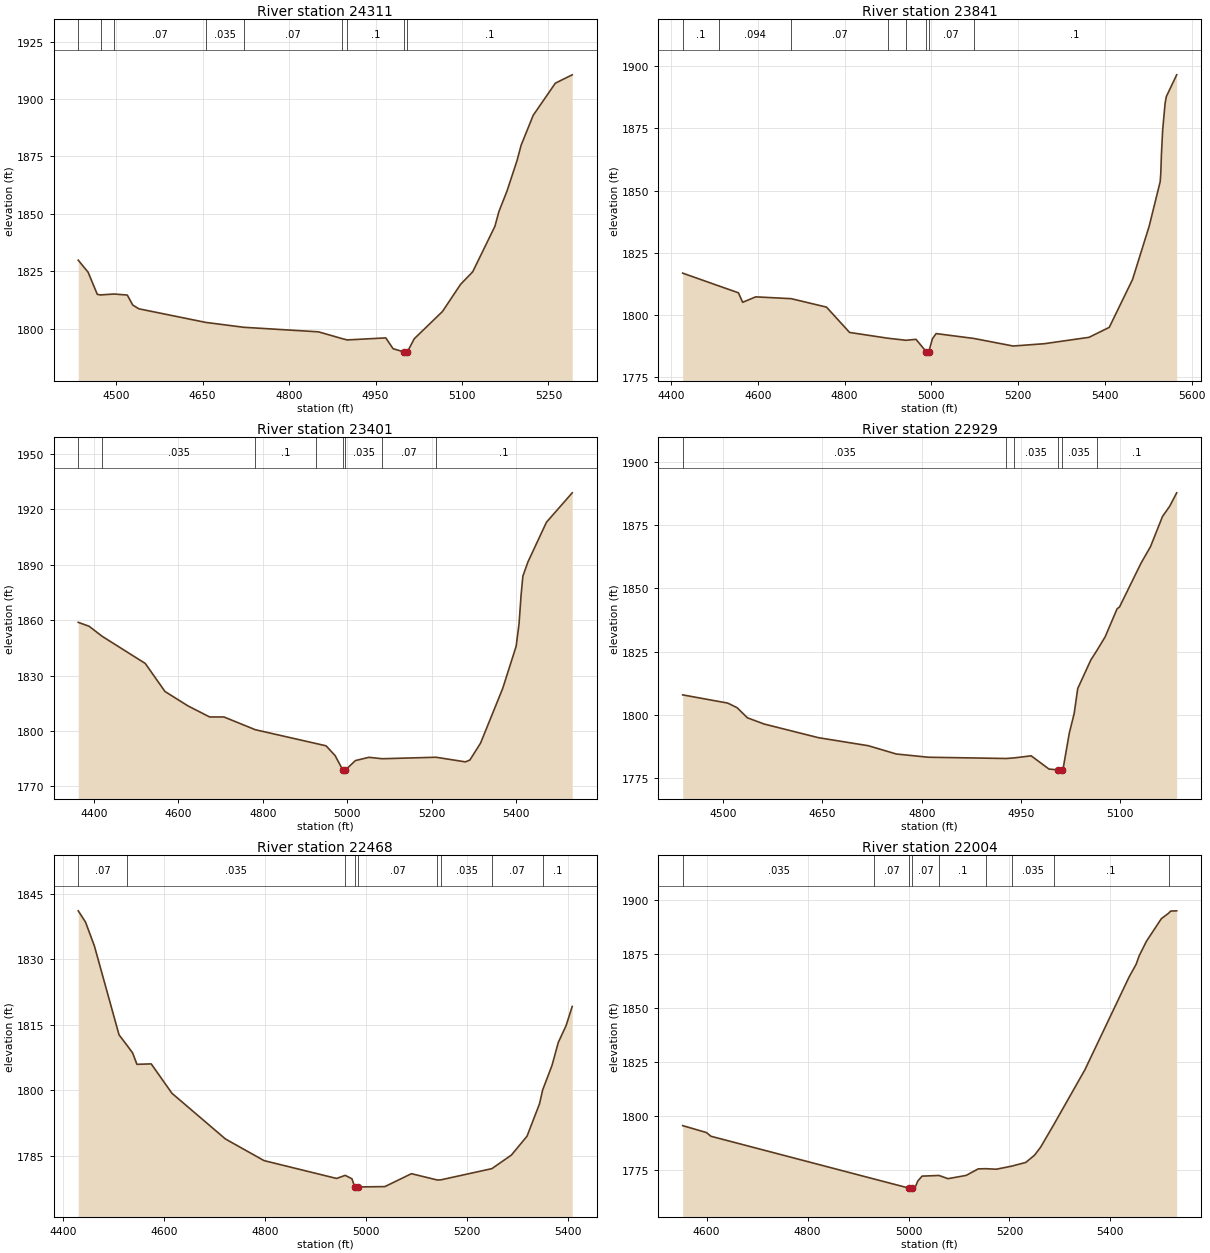
Type RM Length L Ch R = 1,24311,470,470,470
BEGIN DESCRIPTION:
Fall Creek 47.0
END DESCRIPTION:
XS GIS Cut Line= 3
      1908175.02     13883374.98      1908575.00     13882975.00
      1908725.00     13882725.01
#Sta/Elev= 30
  4434.1 1829.85  4451.3 1824.58  4467.2 1814.95  4472.8 1814.72  4496.2 1815.11
  4519.2 1814.66  4528.7 1810.31  4539.3 1808.67  4655.4 1802.75  4721.1 1800.63
  4851.1 1798.64  4892.0 1795.69  4900.7 1795.12  4967.8 1796.00  4980.5 1791.28
  4999.9 1789.87  5000.3 1789.37  5005.2 1789.87  5017.1 1795.61  5066.1 1807.49
  5097.6 1819.34  5118.6 1824.78  5157.1 1844.58  5164.1 1851.03  5178.1 1859.95
  5195.6 1873.29  5202.6 1879.89  5223.6 1892.94  5262.0 1906.93  5291.3 1910.56
#Mann=9,-1,0
  4434.1     0.1       0  4472.8   0.094       0  4496.2    0.07       0
  4655.4   0.035       0  4721.1    0.07       0  4892.0   0.035       0
  4900.7     0.1       0  4999.9    0.05       0  5005.2     0.1       0
Bank Sta=4999.9,5005.2
Exp/Cntr=0.3,0.1

Type RM Length L Ch R = 1,23841,440,440,440
BEGIN DESCRIPTION:
Fall Creek 46.0
END DESCRIPTION:
XS GIS Cut Line= 3
      1908358.74     13883573.36      1908875.00     13883325.00
      1909275.01     13882924.99
#Sta/Elev= 30
  4426.9 1816.78  4511.0 1811.59  4555.3 1808.88  4565.2 1805.05  4595.2 1807.24
  4677.0 1806.51  4758.3 1803.12  4811.6 1792.93  4899.2 1790.62  4941.5 1789.78
  4964.7 1790.16  4988.7 1785.11  4989.1 1784.61  4994.0 1785.11  5002.5 1790.37
  5011.0 1792.47  5097.7 1790.52  5188.5 1787.47  5260.6 1788.40  5363.4 1790.96
  5410.1 1794.97  5463.8 1814.24  5502.0 1835.59  5527.5 1853.58  5528.9 1856.99
  5530.3 1864.36  5533.1 1874.08  5538.8 1885.04  5541.6 1887.76  5565.5 1896.53
#Mann=8,-1,0
  4426.9     0.1       0  4511.0   0.094       0  4677.0    0.07       0
  4899.2     0.1       0  4941.5    0.07       0  4988.7    0.05       0
  4994.0    0.07       0  5097.7     0.1       0
Bank Sta=4988.7,4994
Exp/Cntr=0.3,0.1

Type RM Length L Ch R = 1,23401,472,472,472
BEGIN DESCRIPTION:
Fall Creek 45.0
END DESCRIPTION:
XS GIS Cut Line= 3
      1908772.80     13883974.17      1909225.00     13883525.00
      1909575.01     13883124.99
#Sta/Elev= 30
  4363.3 1858.82  4389.0 1856.69  4420.0 1851.25  4522.0 1836.55  4568.5 1821.41
  4623.1 1813.58  4674.2 1807.62  4708.2 1807.60  4782.3 1800.71  4925.8 1793.25
  4949.8 1791.99  4971.2 1786.68  4989.5 1778.80  4990.0 1778.30  4995.1 1778.80
  5019.1 1784.01  5051.0 1785.77  5082.8 1785.01  5209.9 1785.81  5279.4 1783.32
  5290.0 1784.30  5315.2 1793.42  5367.6 1823.00  5399.5 1845.88  5406.3 1857.91
  5411.4 1874.17  5415.4 1883.82  5427.4 1891.50  5471.2 1912.99  5532.2 1928.90
#Mann=8,-1,0
  4363.3    0.07       0  4420.0   0.035       0  4782.3     0.1       0
  4925.8   0.035       0  4989.5   0.035       0  4995.1   0.035       0
  5082.8    0.07       0  5209.9     0.1       0
Bank Sta=4989.5,4995.1
Exp/Cntr=0.3,0.1

Type RM Length L Ch R = 1,22929,461,461,461
BEGIN DESCRIPTION:
Fall Creek 44.0
END DESCRIPTION:
XS GIS Cut Line= 3
      1909225.02     13883924.98      1909625.00     13883525.00
      1909724.98     13883375.03
#Sta/Elev= 30
  4439.1 1807.81  4507.1 1804.56  4521.3 1802.73  4536.8 1798.73  4562.3 1796.24
  4644.3 1790.83  4719.3 1787.66  4761.7 1784.37  4809.8 1783.09  4927.6 1782.59
  4939.5 1782.82  4965.3 1783.65  4992.2 1778.40  5005.5 1778.08  5006.0 1777.58
  5011.2 1778.08  5014.0 1779.26  5022.9 1792.70  5030.2 1800.40  5035.6 1810.34
  5055.4 1821.67  5064.5 1825.40  5077.0 1830.83  5095.0 1841.93  5098.7 1842.69
  5131.1 1860.01  5145.5 1866.61  5163.6 1878.56  5174.4 1882.59  5185.0 1887.93
#Mann=6,-1,0
  4439.1   0.035       0  4927.6    0.07       0  4939.5   0.035       0
  5005.5   0.035       0  5011.2   0.035       0  5064.5     0.1       0
Bank Sta=5005.5,5011.2
Exp/Cntr=0.3,0.1

Type RM Length L Ch R = 1,22468,464,464,464
BEGIN DESCRIPTION:
Fall Creek 43.0
END DESCRIPTION:
XS GIS Cut Line= 3
      1909424.97     13884325.03      1909825.00     13883925.00
      1909924.99     13883525.03
#Sta/Elev= 30
  4430.1 1841.13  4444.5 1838.55  4462.1 1833.07  4510.9 1812.68  4526.2 1810.35
  4537.8 1808.53  4546.3 1805.92  4574.6 1806.02  4615.6 1799.28  4721.6 1788.79
  4798.0 1783.83  4941.5 1779.74  4958.7 1780.45  4972.0 1779.66  4977.5 1777.79
  4978.0 1777.29  4983.3 1777.79  5037.2 1777.87  5089.7 1780.83  5141.2 1779.38
  5148.4 1779.43  5249.0 1781.99  5287.7 1785.11  5318.6 1789.43  5343.3 1796.85
  5349.6 1800.06  5368.1 1805.68  5380.4 1810.91  5395.9 1814.79  5408.1 1819.20
#Mann=9,-1,0
  4430.1    0.07       0  4526.2   0.035       0  4958.7    0.07       0
  4977.5    0.05       0  4983.3    0.07       0  5141.2     0.1       0
  5148.4   0.035       0  5249.0    0.07       0  5349.6     0.1       0
Bank Sta=4977.5,4983.3
Exp/Cntr=0.3,0.1

Type RM Length L Ch R = 1,22004,418,418,418
BEGIN DESCRIPTION:
Fall Creek 42.0
END DESCRIPTION:
XS GIS Cut Line= 3
      1909825.04     13884324.98      1910225.00     13884125.00
      1910625.02     13883774.99
#Sta/Elev= 30
  4552.6 1795.63  4599.6 1792.43  4608.5 1790.71  4932.3 1770.86  5000.5 1766.70
  5001.0 1766.20  5006.4 1766.70  5013.6 1767.29  5018.5 1770.00  5026.9 1772.23
  5060.4 1772.53  5078.3 1771.05  5114.2 1772.56  5138.1 1775.58  5152.9 1775.67
  5174.0 1775.43  5204.5 1776.86  5232.3 1778.57  5249.7 1781.93  5261.7 1785.64
  5287.7 1796.05  5349.4 1821.49  5437.1 1864.56  5451.0 1870.43  5457.0 1874.34
  5471.2 1881.01  5500.9 1891.55  5515.4 1894.10  5519.3 1895.07  5531.3 1895.19
#Mann=9,-1,0
  4552.6   0.035       0  4932.3    0.07       0  5000.5    0.05       0
  5006.4    0.07       0  5060.4     0.1       0  5152.9    0.07       0
  5204.5   0.035       0  5287.7     0.1       0  5515.4   0.035       0
Bank Sta=5000.5,5006.4
Exp/Cntr=0.3,0.1

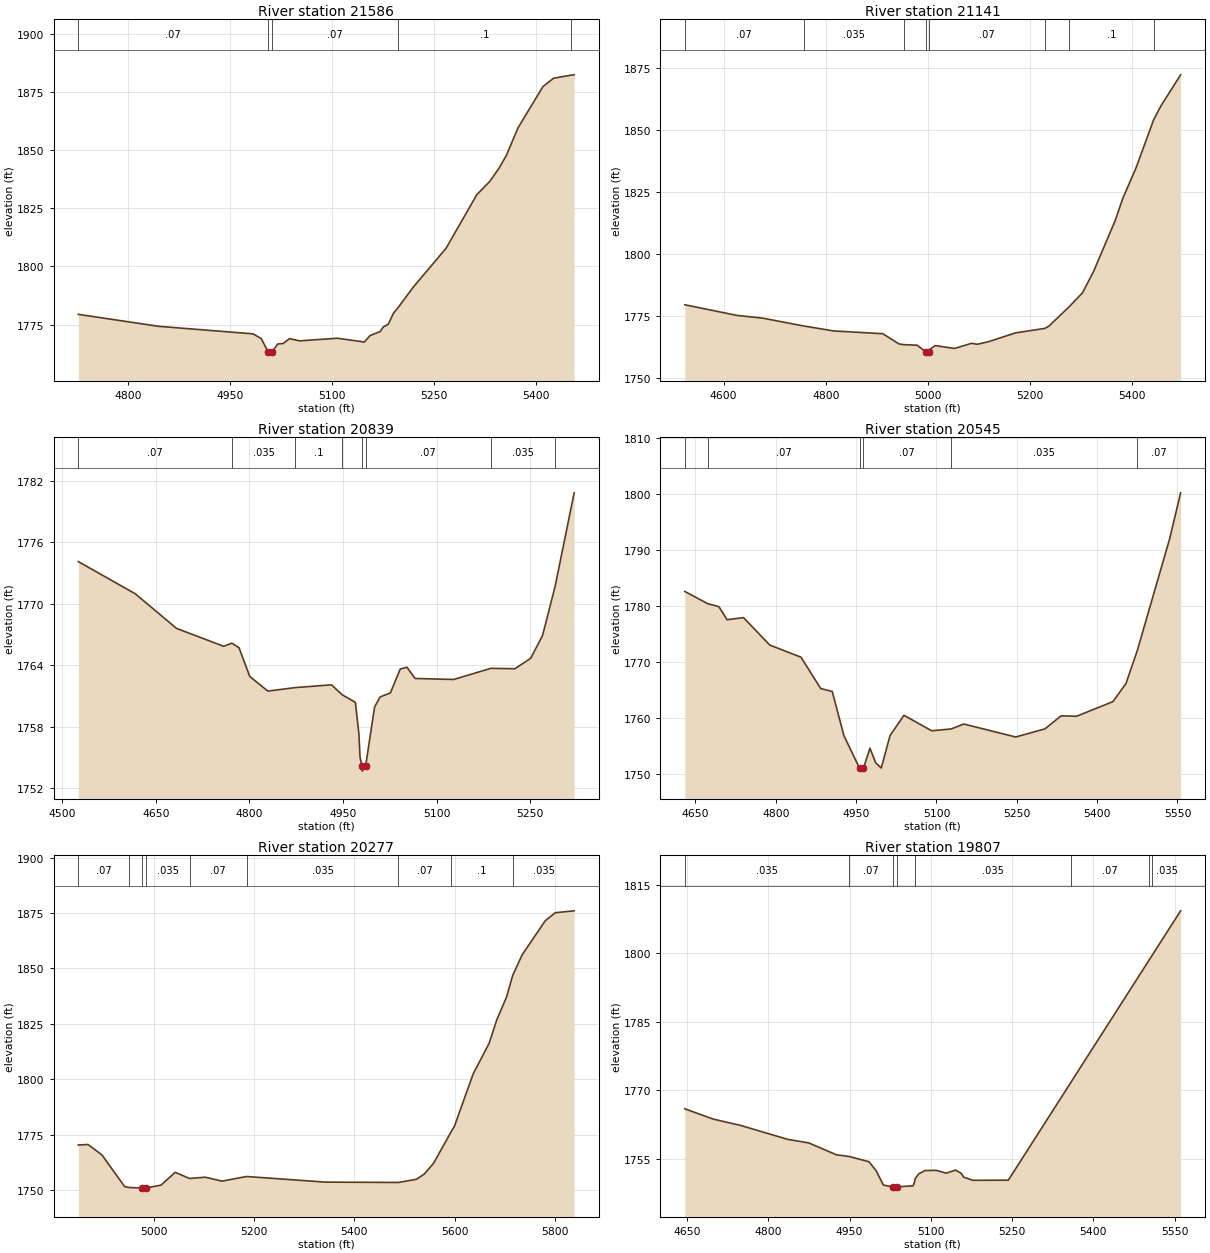
Type RM Length L Ch R = 1,21586,445,445,445
BEGIN DESCRIPTION:
Fall Creek 41.0
END DESCRIPTION:
XS GIS Cut Line= 3
      1910225.01     13884525.00      1910475.00     13884425.00
      1910824.98     13884125.02
#Sta/Elev= 30
  4726.3 1779.41  4844.9 1774.26  4983.8 1771.02  4995.7 1768.97  5005.9 1763.24
  5006.4 1762.74  5011.8 1763.24  5019.8 1766.66  5028.0 1766.88  5037.2 1768.97
  5052.3 1768.01  5107.7 1769.15  5147.5 1767.52  5156.0 1770.29  5170.9 1772.06
  5175.5 1774.02  5182.7 1775.14  5190.6 1780.02  5196.8 1782.14  5219.8 1791.21
  5267.7 1807.75  5313.1 1830.85  5332.2 1836.56  5346.1 1842.36  5356.6 1847.71
  5373.7 1859.54  5410.6 1877.37  5426.2 1880.94  5452.4 1882.28  5456.5 1882.40
#Mann=5,-1,0
  4726.3    0.07       0  5005.9    0.05       0  5011.8    0.07       0
  5196.8     0.1       0  5452.4   0.035       0
Bank Sta=5005.9,5011.8
Exp/Cntr=0.3,0.1

Type RM Length L Ch R = 1,21141,302,302,302
BEGIN DESCRIPTION:
Fall Creek 40.0
END DESCRIPTION:
XS GIS Cut Line= 3
      1910375.03     13884974.98      1910775.00     13884725.00
      1911075.02     13884324.98
#Sta/Elev= 30
  4523.8 1779.55  4626.3 1775.26  4676.3 1774.17  4756.9 1771.00  4815.7 1769.01
  4911.9 1767.89  4943.7 1763.76  4953.1 1763.49  4979.1 1763.25  4996.4 1760.57
  4996.9 1760.07  5002.4 1760.57  5003.1 1761.39  5014.4 1763.11  5052.3 1761.95
  5085.6 1764.01  5097.3 1763.64  5119.4 1764.70  5172.1 1768.23  5229.1 1770.02
  5237.3 1770.94  5276.6 1778.65  5303.1 1784.36  5324.2 1792.66  5366.9 1813.28
  5382.3 1822.47  5408.1 1834.69  5442.6 1854.06  5456.9 1859.66  5495.5 1872.19
#Mann=8,-1,0
  4523.8    0.07       0  4756.9   0.035       0  4953.1    0.07       0
  4996.4    0.05       0  5002.4    0.07       0  5229.1   0.035       0
  5276.6     0.1       0  5442.6   0.035       0
Bank Sta=4996.4,5002.4
Exp/Cntr=0.3,0.1

Type RM Length L Ch R = 1,20839,294,294,294
BEGIN DESCRIPTION:
Fall Creek 39.0
END DESCRIPTION:
XS GIS Cut Line= 3
      1910564.19     13884989.40      1911019.97     13884884.58
      1911125.00     13884574.99
#Sta/Elev= 30
  4525.8 1774.12  4617.1 1770.98  4683.0 1767.61  4758.7 1765.86  4771.8 1766.16
  4783.3 1765.72  4800.6 1762.91  4829.5 1761.49  4873.7 1761.83  4931.5 1762.10
  4948.7 1761.13  4969.8 1760.39  4975.4 1757.32  4977.2 1755.08  4980.2 1754.18
  4980.7 1753.68  4986.2 1754.18  5000.6 1759.94  5009.5 1760.92  5025.9 1761.31
  5041.7 1763.64  5052.5 1763.81  5065.5 1762.72  5127.3 1762.62  5187.1 1763.71
  5225.5 1763.67  5250.8 1764.69  5269.8 1766.92  5289.9 1771.71  5320.4 1780.83
#Mann=8,-1,0
  4525.8    0.07       0  4771.8   0.035       0  4873.7     0.1       0
  4948.7    0.07       0  4980.2    0.05       0  4986.2    0.07       0
  5187.1   0.035       0  5289.9    0.07       0
Bank Sta=4980.2,4986.2
Exp/Cntr=0.3,0.1

Type RM Length L Ch R = 1,20545,268,268,268
BEGIN DESCRIPTION:
Mapping XS 7a3f47a2
END DESCRIPTION:
XS GIS Cut Line= 3
      1911285.38     13885438.10      1911215.95     13885112.62
      1911139.99     13884524.51
#Sta/Elev= 30
  4630.1 1782.64  4673.1 1780.45  4693.7 1779.93  4709.1 1777.59  4739.7 1777.97
  4788.8 1773.07  4847.1 1770.90  4883.9 1765.30  4905.4 1764.79  4927.1 1756.92
  4956.5 1751.06  4957.0 1750.56  4963.6 1751.06  4975.8 1754.66  4986.6 1752.04
  4996.9 1751.12  5013.4 1756.92  5039.3 1760.53  5091.1 1757.76  5127.5 1758.09
  5151.2 1758.97  5248.0 1756.65  5302.7 1758.11  5332.7 1760.43  5361.7 1760.36
  5429.5 1762.97  5453.7 1766.17  5474.7 1771.99  5535.4 1792.04  5555.9 1800.25
#Mann=6,-1,0
  4630.1   0.035       0  4673.1    0.07       0  4956.5    0.05       0
  4963.6    0.07       0  5127.5   0.035       0  5474.7    0.07       0
Bank Sta=4956.5,4963.6
Exp/Cntr=0.3,0.1

Type RM Length L Ch R = 1,20277,470,470,470
BEGIN DESCRIPTION:
Fall Creek 38.0
END DESCRIPTION:
XS GIS Cut Line= 3
      1911425.00     13885224.96      1911425.00     13885075.00
      1911175.00     13884275.01
#Sta/Elev= 30
  4850.2 1770.35  4869.4 1770.62  4897.3 1765.88  4942.3 1751.66  4951.8 1751.19
  4977.7 1750.96  4978.2 1750.46  4984.9 1750.96  5015.0 1752.26  5043.2 1758.04
  5071.8 1755.27  5103.1 1755.84  5136.7 1754.06  5185.5 1756.16  5342.6 1753.62
  5488.2 1753.47  5524.1 1754.90  5539.8 1757.31  5558.1 1762.12  5592.3 1776.00
  5599.6 1778.78  5637.3 1802.58  5668.7 1816.18  5684.4 1827.01  5703.3 1836.97
  5715.9 1846.92  5734.7 1856.19  5780.8 1871.56  5800.7 1875.17  5838.3 1876.02
#Mann=9,-1,0
  4850.2    0.07       0  4951.8   0.035       0  4977.7   0.035       0
  4984.9   0.035       0  5071.8    0.07       0  5185.5   0.035       0
  5488.2    0.07       0  5592.3     0.1       0  5715.9   0.035       0
Bank Sta=4977.7,4984.9
Exp/Cntr=0.3,0.1

Type RM Length L Ch R = 1,19807,430,430,430
BEGIN DESCRIPTION:
Fall Creek 37.0
END DESCRIPTION:
XS GIS Cut Line= 3
      1911775.00     13885125.03      1911775.00     13884775.00
      1911375.01     13884375.01
#Sta/Elev= 30
  4645.6 1765.94  4697.8 1763.69  4748.6 1762.30  4835.8 1759.24  4874.6 1758.46
  4925.6 1755.87  4948.9 1755.50  4985.6 1754.36  4998.6 1752.45  5012.4 1749.23
  5029.5 1748.85  5030.0 1748.35  5036.3 1748.35  5036.8 1748.85  5067.1 1749.07
  5069.2 1749.67  5071.1 1750.64  5077.7 1751.69  5088.8 1752.41  5109.5 1752.47
  5128.6 1751.85  5145.5 1752.52  5155.6 1751.86  5160.9 1750.96  5177.9 1750.28
  5243.1 1750.31  5358.5 1771.70  5502.2 1798.33  5509.0 1799.59  5561.3 1809.28
#Mann=8,-1,0
  4645.6   0.035       0  4948.9    0.07       0  5029.5    0.05       0
  5036.8    0.07       0  5071.1   0.035       0  5358.5    0.07       0
  5502.2     0.1       0  5509.0   0.035       0
Bank Sta=5029.5,5036.8
Exp/Cntr=0.3,0.1

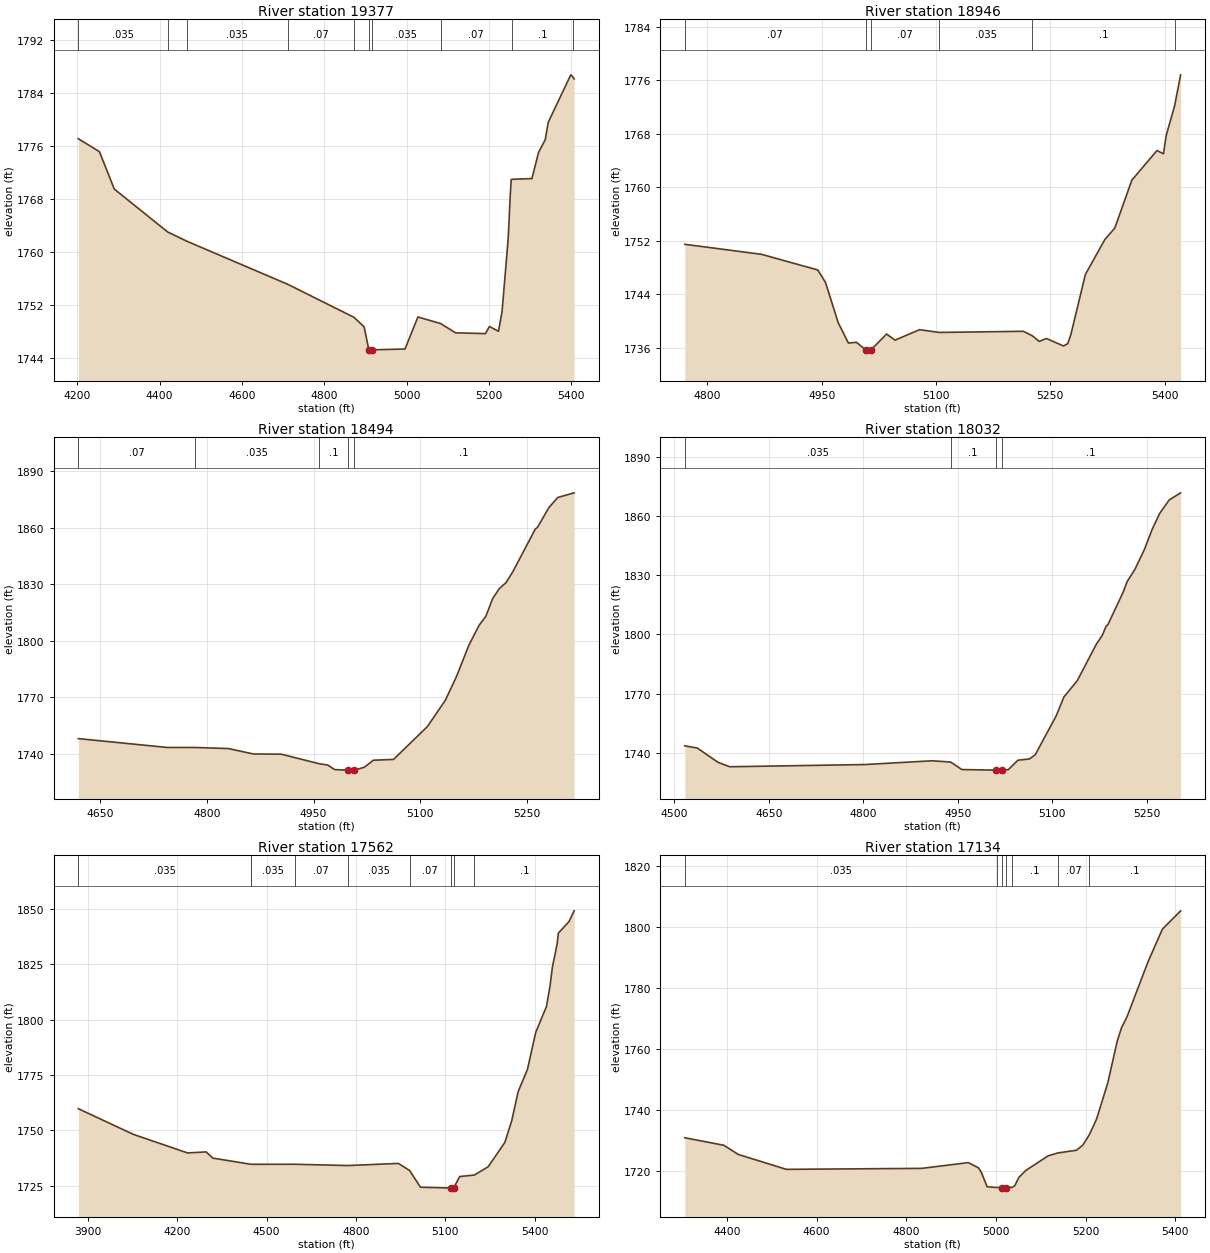
Type RM Length L Ch R = 1,19377,431,431,431
BEGIN DESCRIPTION:
Fall Creek 36.0
END DESCRIPTION:
XS GIS Cut Line= 3
      1912075.00     13885324.98      1912025.00     13884525.00
      1911675.04     13884325.02
#Sta/Elev= 30
  4202.6 1777.05  4253.8 1775.11  4289.9 1769.46  4419.8 1762.97  4467.1 1761.56
  4711.0 1755.09  4872.5 1750.09  4897.0 1748.65  4908.4 1745.19  4908.9 1744.69
  4915.7 1745.19  4996.2 1745.31  5027.6 1750.15  5083.0 1749.15  5119.2 1747.75
  5191.7 1747.64  5201.3 1748.71  5223.3 1747.99  5232.1 1750.99  5247.0 1762.04
  5251.9 1768.49  5254.3 1770.87  5255.7 1770.93  5304.6 1771.04  5320.8 1775.00
  5336.9 1776.90  5344.2 1779.53  5399.0 1786.70  5403.8 1786.41  5407.2 1786.08
#Mann=10,-1,0
  4202.6   0.035       0  4419.8    0.07       0  4467.1   0.035       0
  4711.0    0.07       0  4872.5   0.035       0  4908.4   0.035       0
  4915.7   0.035       0  5083.0    0.07       0  5255.7     0.1       0
  5403.8    0.07       0
Bank Sta=4908.4,4915.7
Exp/Cntr=0.3,0.1

Type RM Length L Ch R = 1,18946,452,452,452
BEGIN DESCRIPTION:
Fall Creek 35.0
END DESCRIPTION:
XS GIS Cut Line= 3
      1912325.01     13884724.98      1912425.00     13884525.00
      1912575.00     13884124.99
#Sta/Elev= 30
  4770.3 1751.49  4871.0 1749.99  4944.8 1747.66  4954.9 1745.82  4971.7 1739.78
  4985.1 1736.74  4995.6 1736.86  5007.5 1735.74  5008.0 1735.24  5014.8 1735.74
  5035.2 1738.09  5046.3 1737.18  5078.4 1738.74  5104.6 1738.33  5214.7 1738.50
  5226.5 1737.83  5235.4 1736.99  5245.0 1737.42  5267.4 1736.31  5272.9 1736.65
  5277.0 1737.99  5296.1 1746.99  5321.7 1752.21  5334.7 1753.91  5357.1 1761.07
  5390.1 1765.49  5398.6 1765.00  5402.0 1767.66  5413.2 1772.16  5421.1 1776.79
#Mann=6,-1,0
  4770.3    0.07       0  5007.5    0.05       0  5014.8    0.07       0
  5104.6   0.035       0  5226.5     0.1       0  5413.2    0.07       0
Bank Sta=5007.5,5014.8
Exp/Cntr=0.3,0.1

Type RM Length L Ch R = 1,18494,462,462,462
BEGIN DESCRIPTION:
Fall Creek 34.0
END DESCRIPTION:
XS GIS Cut Line= 3
      1912625.00     13884675.00      1912775.00     13884325.00
      1912874.99     13884025.02
#Sta/Elev= 30
  4619.3 1747.95  4744.6 1743.24  4783.4 1743.24  4830.3 1742.67  4865.3 1739.80
  4904.5 1739.69  4958.3 1734.57  4969.8 1733.92  4979.6 1731.50  4997.8 1731.18
  4998.3 1730.68  5006.9 1731.18  5021.3 1732.73  5034.0 1736.46  5062.4 1736.91
  5109.8 1754.27  5135.1 1768.23  5151.0 1781.01  5168.1 1797.42  5182.6 1808.11
  5192.1 1812.87  5201.6 1822.22  5211.0 1827.62  5220.5 1830.80  5230.0 1836.53
  5261.6 1859.22  5264.8 1860.18  5280.6 1870.58  5293.3 1876.05  5316.3 1878.51
#Mann=5,-1,0
  4619.3    0.07       0  4783.4   0.035       0  4958.3     0.1       0
  4997.8    0.05       0  5006.9     0.1       0
Bank Sta=4997.8,5006.9
Exp/Cntr=0.3,0.1

Type RM Length L Ch R = 1,18032,470,470,470
BEGIN DESCRIPTION:
Fall Creek 33.0
END DESCRIPTION:
XS GIS Cut Line= 3
      1912860.21     13884791.85      1913175.00     13884425.00
      1913224.99     13884125.04
#Sta/Elev= 30
  4516.6 1743.48  4536.4 1742.40  4569.3 1735.13  4588.1 1732.88  4802.5 1734.00
  4909.2 1735.90  4938.7 1735.28  4956.7 1731.46  5010.7 1731.16  5011.2 1730.66
  5019.9 1731.16  5030.5 1731.43  5045.7 1736.20  5064.0 1736.84  5073.1 1738.94
  5106.6 1758.78  5118.7 1768.26  5140.0 1776.59  5170.4 1795.18  5179.6 1799.51
  5185.6 1804.07  5188.7 1805.04  5213.0 1821.59  5219.1 1826.77  5231.3 1832.92
  5246.5 1843.05  5258.6 1853.11  5270.8 1861.41  5286.0 1868.25  5304.1 1871.86
#Mann=4,-1,0
  4516.6   0.035       0  4938.7     0.1       0  5010.7    0.05       0
  5019.9     0.1       0
Bank Sta=5010.7,5019.9
Exp/Cntr=0.3,0.1

Type RM Length L Ch R = 1,17562,428,428,428
BEGIN DESCRIPTION:
Fall Creek 32.0
END DESCRIPTION:
XS GIS Cut Line= 3
      1912725.01     13885524.99      1913525.00     13884725.00
      1913875.03     13884324.97
#Sta/Elev= 30
  3868.9 1759.76  4052.9 1748.17  4235.3 1739.74  4297.6 1740.21  4320.2 1737.40
  4447.9 1734.60  4448.1 1734.60  4594.6 1734.62  4772.9 1734.04  4942.4 1735.00
  4980.0 1731.80  5016.4 1724.23  5118.3 1723.87  5118.8 1723.37  5127.7 1723.87
  5147.9 1729.06  5197.1 1729.74  5243.6 1733.51  5299.4 1744.52  5322.4 1754.30
  5344.1 1767.51  5375.1 1777.52  5403.0 1794.32  5438.9 1805.98  5450.9 1815.30
  5458.8 1823.81  5474.8 1834.36  5478.8 1839.17  5514.6 1844.42  5531.8 1849.27
#Mann=9,-1,0
  3868.9   0.035       0  4447.9    0.07       0  4448.1   0.035       0
  4594.6    0.07       0  4772.9   0.035       0  4980.0    0.07       0
  5118.3    0.05       0  5127.7    0.07       0  5197.1     0.1       0
Bank Sta=5118.3,5127.7
Exp/Cntr=0.3,0.1

Type RM Length L Ch R = 1,17134,467,467,467
BEGIN DESCRIPTION:
Fall Creek 31.0
END DESCRIPTION:
XS GIS Cut Line= 3
      1913233.63     13885189.80      1913875.00     13884925.00
      1913975.00     13884524.99
#Sta/Elev= 30
  4305.8 1731.05  4392.9 1728.59  4425.3 1725.57  4532.4 1720.70  4834.3 1721.02
  4938.1 1722.90  4960.9 1721.22  4967.4 1719.75  4980.3 1714.99  5002.5 1714.75
  5012.6 1714.72  5013.1 1714.22  5022.0 1714.72  5036.9 1714.82  5042.1 1715.38
  5051.3 1718.10  5066.8 1720.36  5116.3 1725.11  5137.5 1726.05  5179.6 1726.96
  5193.6 1728.61  5208.3 1732.02  5224.5 1737.18  5249.3 1748.94  5270.9 1762.88
  5280.2 1767.09  5292.5 1770.71  5338.9 1788.55  5371.3 1799.37  5412.0 1805.38
#Mann=7,-1,0
  4305.8   0.035       0  5002.5    0.07       0  5012.6   0.035       0
  5022.0    0.07       0  5036.9     0.1       0  5137.5    0.07       0
  5208.3     0.1       0
Bank Sta=5012.6,5022
Exp/Cntr=0.3,0.1

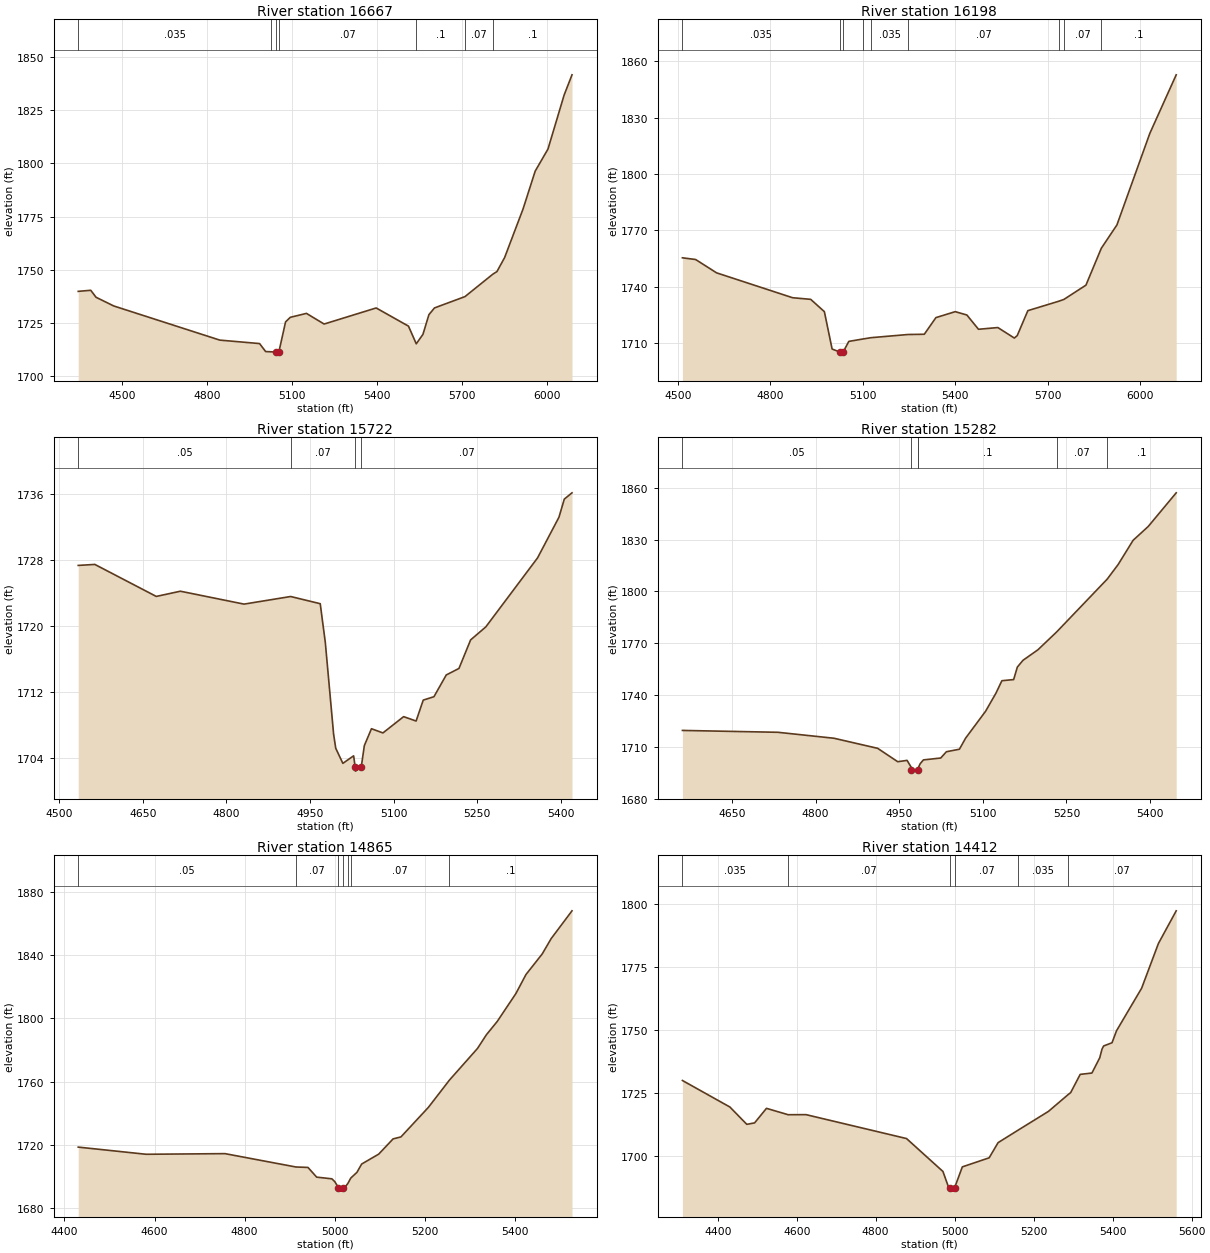
Type RM Length L Ch R = 1,16667,469,469,469
BEGIN DESCRIPTION:
Fall Creek 30.0
END DESCRIPTION:
XS GIS Cut Line= 3
      1913100.58     13885452.67      1913725.00     13885275.00
      1914817.92     13885242.69
#Sta/Elev= 30
  4346.2 1739.91  4390.4 1740.41  4409.1 1737.13  4471.5 1733.05  4846.0 1717.00
  4986.2 1715.38  5007.5 1711.64  5028.2 1711.50  5044.8 1711.39  5045.3 1710.89
  5054.2 1711.39  5077.9 1725.54  5094.6 1727.71  5151.6 1729.56  5214.0 1724.56
  5397.7 1732.11  5511.7 1723.57  5539.2 1715.27  5562.8 1719.72  5583.8 1728.95
  5603.6 1732.13  5711.1 1737.44  5809.8 1748.02  5823.9 1749.20  5850.9 1755.75
  5916.0 1778.59  5958.9 1796.39  6004.0 1806.76  6061.0 1832.12  6088.8 1841.63
#Mann=7,-1,0
  4346.2   0.035       0  5028.2    0.07       0  5044.8   0.035       0
  5054.2    0.07       0  5539.2     0.1       0  5711.1    0.07       0
  5809.8     0.1       0
Bank Sta=5044.8,5054.2
Exp/Cntr=0.3,0.1

Type RM Length L Ch R = 1,16198,476,476,476
BEGIN DESCRIPTION:
Fall Creek 29.0
END DESCRIPTION:
XS GIS Cut Line= 3
      1913403.26     13885936.16      1913775.00     13885625.00
      1914841.92     13885298.29
#Sta/Elev= 30
  4515.3 1755.41  4558.0 1754.51  4626.0 1747.41  4872.4 1734.17  4931.1 1733.31
  4975.4 1726.76  5000.5 1706.88  5026.4 1705.19  5026.9 1704.69  5036.0 1705.19
  5054.6 1710.93  5100.4 1712.21  5126.3 1712.90  5246.7 1714.60  5299.3 1714.73
  5337.0 1723.59  5399.7 1726.76  5437.4 1724.97  5475.0 1717.38  5537.8 1718.30
  5591.1 1712.71  5600.5 1713.99  5635.0 1727.29  5735.1 1732.30  5751.8 1733.26
  5823.3 1740.86  5873.2 1760.51  5923.7 1772.89  6030.4 1821.63  6115.9 1852.78
#Mann=9,-1,0
  4515.3   0.035       0  5026.4   0.035       0  5036.0   0.035       0
  5100.4    0.05       0  5126.3   0.035       0  5246.7    0.07       0
  5735.1     0.1       0  5751.8    0.07       0  5873.2     0.1       0
Bank Sta=5026.4,5036
Exp/Cntr=0.3,0.1

Type RM Length L Ch R = 1,15722,440,440,440
BEGIN DESCRIPTION:
Fall Creek 28.0
END DESCRIPTION:
XS GIS Cut Line= 3
      1913825.41     13886121.96      1914175.00     13885825.00
      1914575.01     13885675.00
#Sta/Elev= 30
  4534.3 1727.32  4564.1 1727.44  4674.3 1723.57  4717.6 1724.20  4831.8 1722.64
  4915.4 1723.56  4968.5 1722.69  4977.6 1718.01  4992.5 1706.91  4996.3 1705.21
  5009.1 1703.38  5028.4 1704.29  5031.2 1702.94  5031.7 1702.44  5042.1 1702.94
  5047.6 1705.52  5060.4 1707.57  5081.0 1707.06  5118.1 1709.03  5140.5 1708.50
  5153.3 1711.03  5172.5 1711.44  5194.6 1714.07  5217.4 1714.86  5238.3 1718.31
  5265.5 1719.88  5358.4 1728.23  5396.8 1733.15  5406.4 1735.34  5420.2 1736.10
#Mann=4,-1,0
  4534.3    0.05       0  4915.4    0.07       0  5031.2    0.05       0
  5042.1    0.07       0
Bank Sta=5031.2,5042.1
Exp/Cntr=0.3,0.1

Type RM Length L Ch R = 1,15282,417,417,417
BEGIN DESCRIPTION:
Fall Creek 27.0
END DESCRIPTION:
XS GIS Cut Line= 3
      1914133.25     13886272.59      1914525.00     13886075.00
      1914925.02     13885874.99
#Sta/Elev= 30
  4561.0 1719.58  4732.2 1718.50  4833.0 1715.05  4911.3 1709.22  4947.3 1701.47
  4964.1 1702.23  4971.7 1698.16  4972.0 1696.52  4972.5 1696.02  4982.9 1696.52
  4983.7 1697.59  4987.6 1700.31  4993.4 1702.52  5024.5 1703.61  5034.6 1707.24
  5058.0 1708.70  5069.1 1715.10  5105.0 1730.69  5123.7 1741.23  5134.2 1748.35
  5155.3 1749.02  5162.0 1756.27  5172.1 1760.17  5198.9 1766.27  5232.5 1776.59
  5323.3 1807.20  5342.8 1815.60  5369.6 1829.60  5396.8 1837.64  5447.0 1857.11
#Mann=6,-1,0
  4561.0    0.05       0  4972.0    0.05       0  4982.9    0.05       0
  4983.7     0.1       0  5232.5    0.07       0  5323.3     0.1       0
Bank Sta=4972,4982.9
Exp/Cntr=0.3,0.1

Type RM Length L Ch R = 1,14865,453,453,453
BEGIN DESCRIPTION:
Fall Creek 26.0
END DESCRIPTION:
XS GIS Cut Line= 3
      1914183.69     13886584.91      1914725.00     13886425.00
      1915074.97     13886025.03
#Sta/Elev= 30
  4430.6 1718.71  4581.2 1714.19  4756.4 1714.59  4913.7 1706.16  4940.5 1705.88
  4959.8 1699.76  4993.6 1698.69  5000.2 1696.84  5005.8 1694.18  5006.4 1692.68
  5006.9 1692.18  5017.4 1692.68  5021.8 1693.09  5029.0 1695.76  5035.6 1699.19
  5049.1 1702.75  5059.7 1708.04  5097.5 1714.28  5129.4 1723.90  5146.9 1725.16
  5207.8 1743.82  5254.6 1761.07  5316.8 1781.03  5336.7 1789.73  5360.6 1798.08
  5402.0 1815.70  5424.4 1827.72  5460.3 1840.65  5480.2 1850.35  5526.5 1867.92
#Mann=7,-1,0
  4430.6    0.05       0  4913.7    0.07       0  5006.4    0.05       0
  5017.4    0.07       0  5029.0     0.1       0  5035.6    0.07       0
  5254.6     0.1       0
Bank Sta=5006.4,5017.4
Exp/Cntr=0.3,0.1

Type RM Length L Ch R = 1,14412,474,474,474
BEGIN DESCRIPTION:
Fall Creek 25.0
END DESCRIPTION:
XS GIS Cut Line= 3
      1914326.12     13887234.02      1914875.00     13886825.00
      1915275.00     13886425.00
#Sta/Elev= 30
  4310.7 1729.96  4430.9 1719.40  4473.7 1712.51  4493.4 1713.09  4523.5 1718.88
  4578.4 1716.34  4623.7 1716.37  4878.1 1706.86  4970.3 1693.76  4982.9 1688.24
  4988.5 1687.24  4989.0 1686.74  4999.7 1687.24  5019.4 1695.59  5087.3 1699.20
  5109.9 1705.23  5160.9 1710.23  5237.2 1717.64  5286.5 1724.24  5293.8 1725.16
  5317.8 1732.39  5347.5 1732.92  5367.3 1738.99  5373.0 1742.41  5377.2 1743.69
  5398.4 1744.97  5409.8 1749.74  5473.4 1766.68  5515.8 1784.43  5560.9 1797.45
#Mann=6,-1,0
  4310.7   0.035       0  4578.4    0.07       0  4988.5    0.05       0
  4999.7    0.07       0  5160.9   0.035       0  5286.5    0.07       0
Bank Sta=4988.5,4999.7
Exp/Cntr=0.3,0.1