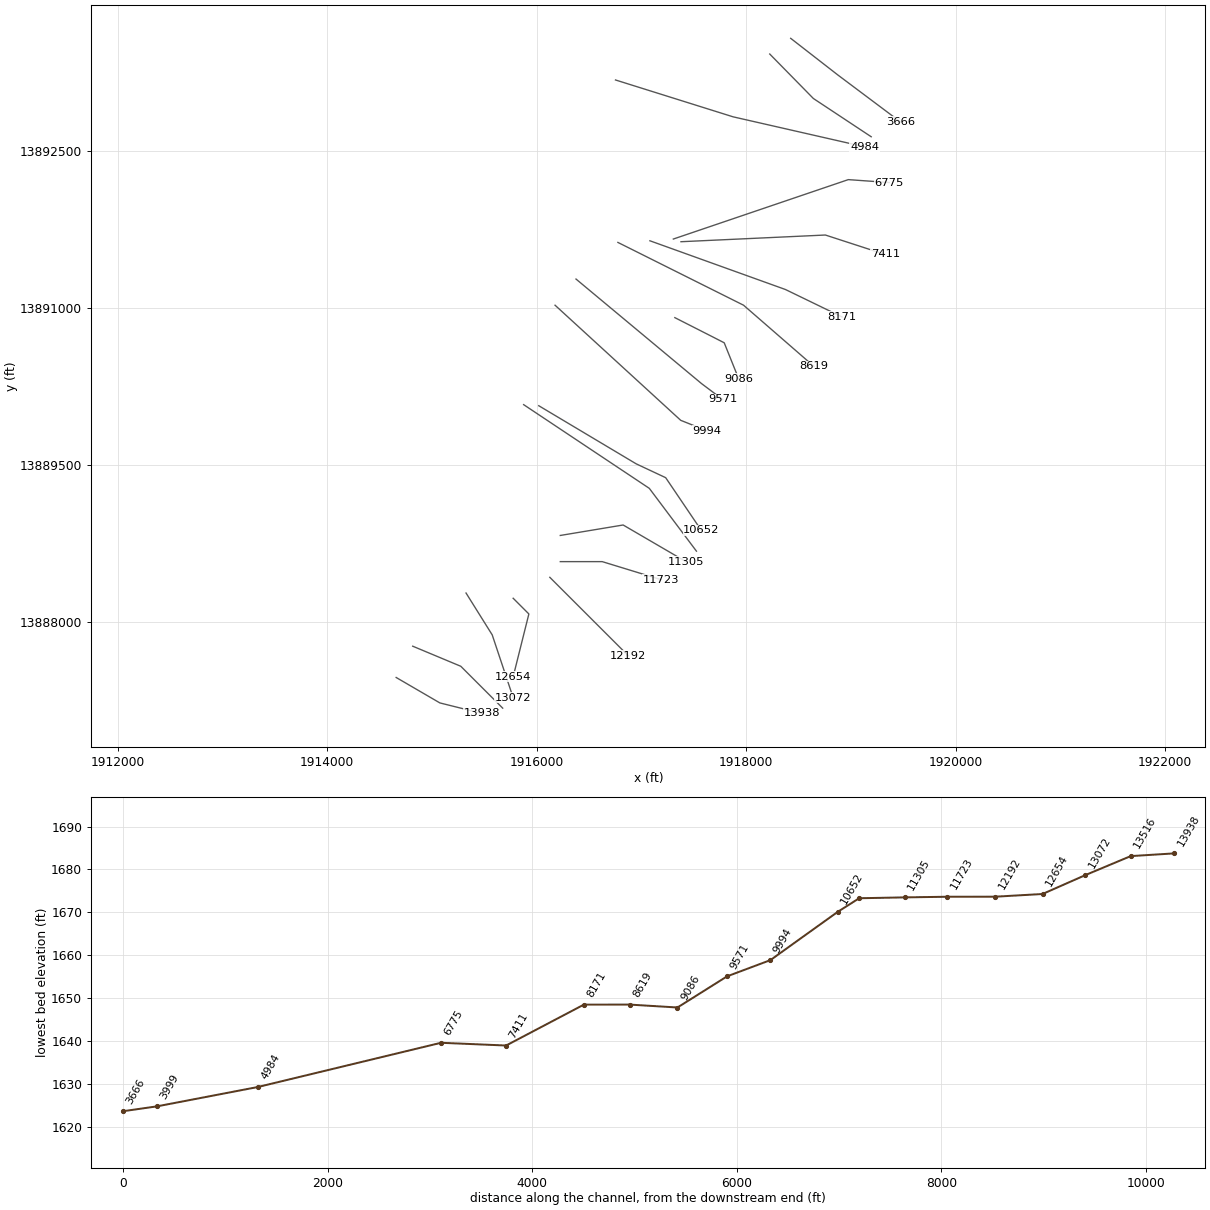
HEC-RAS study Fall Creek.prj: Fall Creek Base Level Engineering

--- Fall Creek.g01 (geometry) --- (continued)

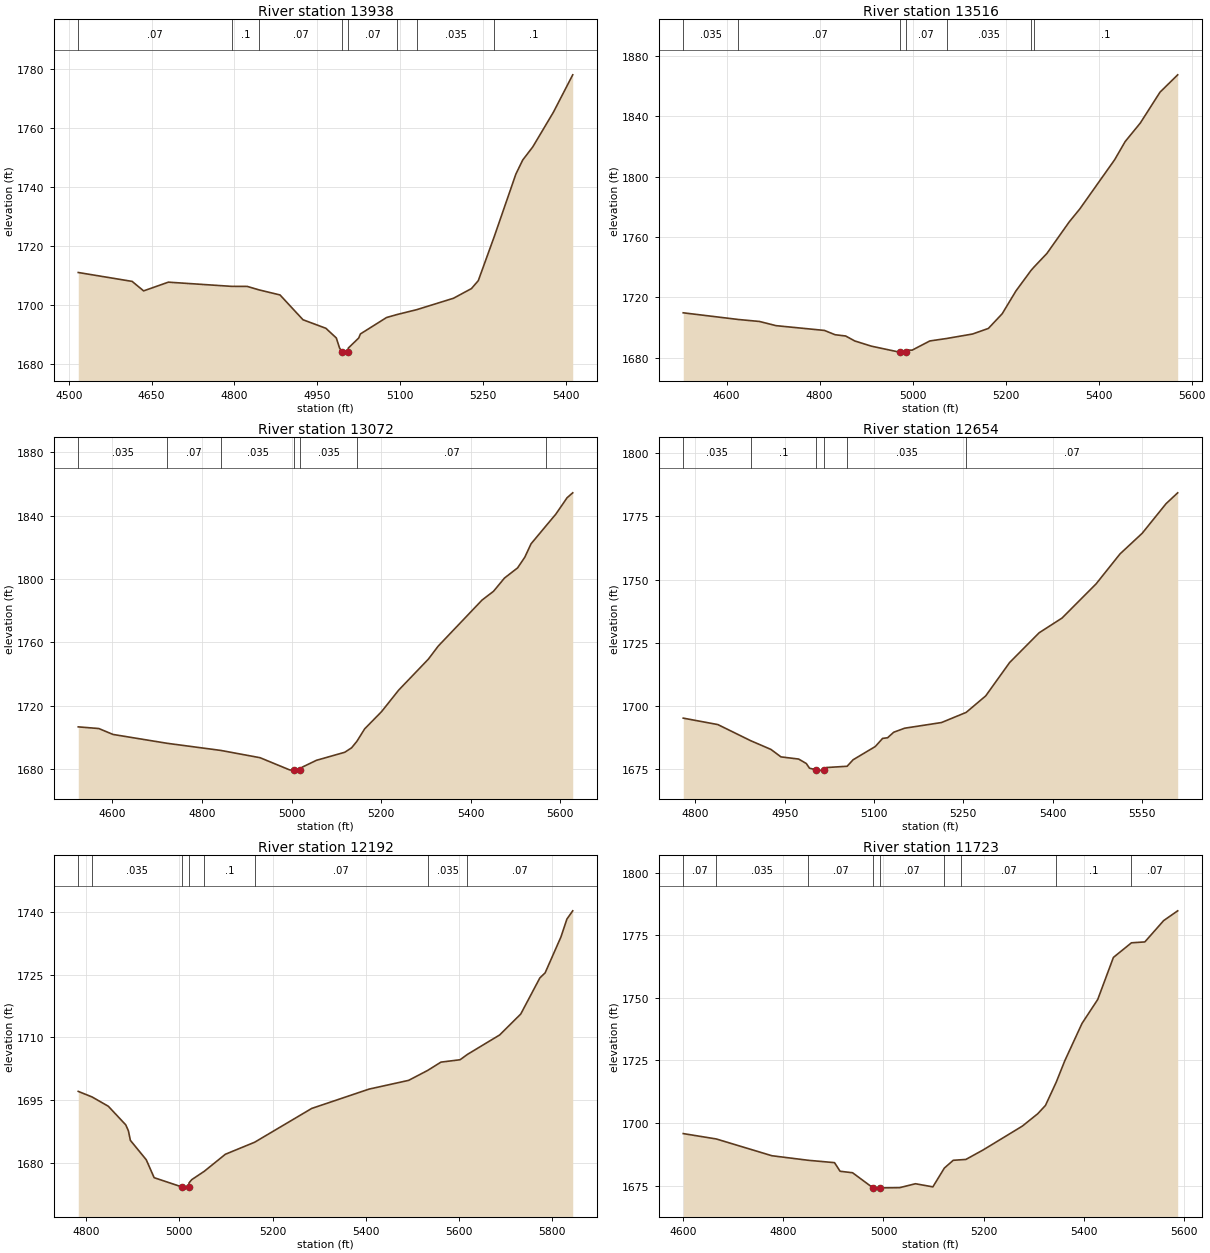
Type RM Length L Ch R = 1,13938,422,422,422
BEGIN DESCRIPTION:
Fall Creek 24.0
END DESCRIPTION:
XS GIS Cut Line= 3
      1914657.86     13887467.95      1915075.00     13887225.00
      1915474.96     13887125.01
#Sta/Elev= 30
  4517.3 1711.11  4614.8 1708.09  4635.6 1704.87  4680.4 1707.83  4795.1 1706.40
  4823.1 1706.39  4844.7 1705.20  4882.5 1703.49  4924.1 1695.07  4965.5 1692.18
  4984.4 1688.89  4990.3 1685.46  4994.6 1684.25  4995.1 1683.75  5005.8 1684.25
  5006.0 1685.45  5024.9 1688.87  5028.0 1690.26  5075.3 1695.83  5094.4 1696.85
  5130.0 1698.50  5196.5 1702.37  5229.0 1705.65  5241.4 1708.35  5270.4 1723.37
  5309.4 1744.50  5321.8 1749.28  5340.0 1753.73  5377.4 1765.52  5412.3 1778.18
#Mann=8,-1,0
  4517.3    0.07       0  4795.1     0.1       0  4844.7    0.07       0
  4994.6    0.05       0  5005.8    0.07       0  5094.4     0.1       0
  5130.0   0.035       0  5270.4     0.1       0
Bank Sta=4994.6,5005.8
Exp/Cntr=0.3,0.1

Type RM Length L Ch R = 1,13516,444,444,444
BEGIN DESCRIPTION:
Fall Creek 23.0
END DESCRIPTION:
XS GIS Cut Line= 3
      1914815.88     13887766.92      1915275.00     13887575.00
      1915675.00     13887175.00
#Sta/Elev= 30
  4506.7 1709.82  4625.5 1705.39  4670.6 1704.09  4706.4 1701.31  4810.4 1698.15
  4833.2 1695.31  4856.0 1694.46  4875.5 1691.19  4911.2 1687.74  4973.9 1683.62
  4974.4 1683.12  4985.2 1683.62  4989.3 1685.10  4999.0 1685.10  5037.0 1691.18
  5073.3 1692.82  5128.9 1695.78  5162.9 1699.48  5192.6 1709.20  5222.3 1724.36
  5254.3 1737.76  5260.4 1739.93  5288.7 1749.12  5336.8 1770.05  5359.5 1778.61
  5434.4 1811.19  5457.0 1823.23  5489.6 1835.51  5532.0 1855.96  5570.0 1867.44
#Mann=7,-1,0
  4506.7   0.035       0  4625.5    0.07       0  4973.9    0.05       0
  4985.2    0.07       0  5073.3   0.035       0  5254.3    0.07       0
  5260.4     0.1       0
Bank Sta=4973.9,4985.2
Exp/Cntr=0.3,0.1

Type RM Length L Ch R = 1,13072,418,418,418
BEGIN DESCRIPTION:
Fall Creek 22.0
END DESCRIPTION:
XS GIS Cut Line= 3
      1915324.98     13888275.04      1915575.00     13887875.00
      1915775.00     13887275.00
#Sta/Elev= 30
  4523.7 1706.62  4569.6 1705.57  4601.3 1701.84  4722.3 1696.24  4841.8 1691.76
  4929.6 1687.16  4995.6 1679.47  5006.5 1679.18  5007.0 1678.68  5019.5 1679.18
  5024.0 1681.21  5055.7 1685.52  5118.9 1690.59  5134.0 1693.39  5145.7 1697.41
  5163.2 1705.34  5201.1 1716.28  5239.1 1729.78  5305.5 1749.37  5327.6 1757.64
  5425.5 1786.70  5450.9 1792.18  5475.5 1800.58  5504.7 1806.97  5520.8 1813.68
  5534.8 1822.18  5568.3 1833.55  5590.1 1840.89  5615.4 1851.31  5627.9 1854.38
#Mann=7,-1,0
  4523.7   0.035       0  4722.3    0.07       0  4841.8   0.035       0
  5006.5   0.035       0  5019.5   0.035       0  5145.7    0.07       0
  5568.3     0.1       0
Bank Sta=5006.5,5019.5
Exp/Cntr=0.3,0.1

Type RM Length L Ch R = 1,12654,462,462,462
BEGIN DESCRIPTION:
Fall Creek 21.0
END DESCRIPTION:
XS GIS Cut Line= 3
      1915775.00     13888225.00      1915925.00     13888075.00
      1915775.00     13887475.00
#Sta/Elev= 30
  4779.5 1695.23  4837.7 1692.68  4892.8 1686.31  4926.8 1682.87  4943.7 1679.91
  4973.4 1679.05  4986.2 1677.30  4991.6 1675.45  5002.5 1674.78  5003.0 1674.28
  5015.5 1674.78  5020.0 1675.70  5054.8 1676.20  5064.9 1678.78  5102.1 1684.00
  5114.4 1687.22  5122.8 1687.47  5133.0 1689.65  5151.5 1691.25  5213.4 1693.49
  5254.8 1697.50  5287.6 1704.02  5327.8 1717.22  5377.3 1728.96  5415.8 1734.79
  5473.1 1748.32  5513.3 1760.17  5550.4 1768.29  5590.6 1780.02  5610.1 1784.30
#Mann=6,-1,0
  4779.5   0.035       0  4892.8     0.1       0  5002.5    0.05       0
  5015.5     0.1       0  5054.8   0.035       0  5254.8    0.07       0
Bank Sta=5002.5,5015.5
Exp/Cntr=0.3,0.1

Type RM Length L Ch R = 1,12192,469,469,469
BEGIN DESCRIPTION:
Fall Creek 20.0
END DESCRIPTION:
XS GIS Cut Line= 3
      1916125.03     13888424.97      1916275.00     13888275.00
      1916874.99     13887675.01
#Sta/Elev= 30
  4783.1 1697.06  4812.7 1695.73  4847.6 1693.50  4885.0 1689.04  4890.7 1687.60
  4894.9 1685.33  4928.9 1680.69  4945.9 1676.39  5006.0 1674.15  5006.5 1673.65
  5020.1 1674.15  5020.8 1675.16  5026.5 1675.92  5053.5 1677.93  5098.6 1682.00
  5161.4 1684.88  5283.9 1692.98  5406.9 1697.61  5491.7 1699.70  5532.7 1702.09
  5561.0 1704.07  5602.1 1704.64  5617.8 1705.92  5686.9 1710.57  5732.2 1715.59
  5773.2 1724.24  5784.5 1725.45  5818.4 1734.04  5831.2 1738.33  5843.7 1740.31
#Mann=8,-1,0
  4783.1    0.07       0  4812.7   0.035       0  5006.0   0.035       0
  5020.1   0.035       0  5053.5     0.1       0  5161.4    0.07       0
  5532.7   0.035       0  5617.8    0.07       0
Bank Sta=5006,5020.1
Exp/Cntr=0.3,0.1

Type RM Length L Ch R = 1,11723,418,418,418
BEGIN DESCRIPTION:
Fall Creek 19.0
END DESCRIPTION:
XS GIS Cut Line= 3
      1916225.04     13888575.00      1916625.00     13888575.00
      1917186.85     13888402.84
#Sta/Elev= 30
  4600.0 1695.81  4666.0 1693.67  4777.1 1686.97  4850.2 1685.14  4902.2 1684.21
  4913.3 1680.77  4938.2 1680.18  4979.1 1674.14  4979.6 1673.64  4993.3 1674.14
  5032.2 1674.22  5063.8 1675.79  5098.6 1674.54  5121.5 1682.04  5139.3 1685.15
  5154.1 1685.35  5164.4 1685.48  5199.0 1689.28  5277.4 1698.81  5308.1 1703.74
  5323.5 1707.05  5344.9 1716.29  5362.1 1724.88  5396.5 1739.79  5427.9 1749.35
  5459.2 1766.14  5495.2 1771.97  5522.0 1772.33  5559.6 1780.85  5587.6 1784.74
#Mann=9,-1,0
  4600.0    0.07       0  4666.0   0.035       0  4850.2    0.07       0
  4979.1    0.05       0  4993.3    0.07       0  5121.5     0.1       0
  5154.1    0.07       0  5344.9     0.1       0  5495.2    0.07       0
Bank Sta=4979.1,4993.3
Exp/Cntr=0.3,0.1

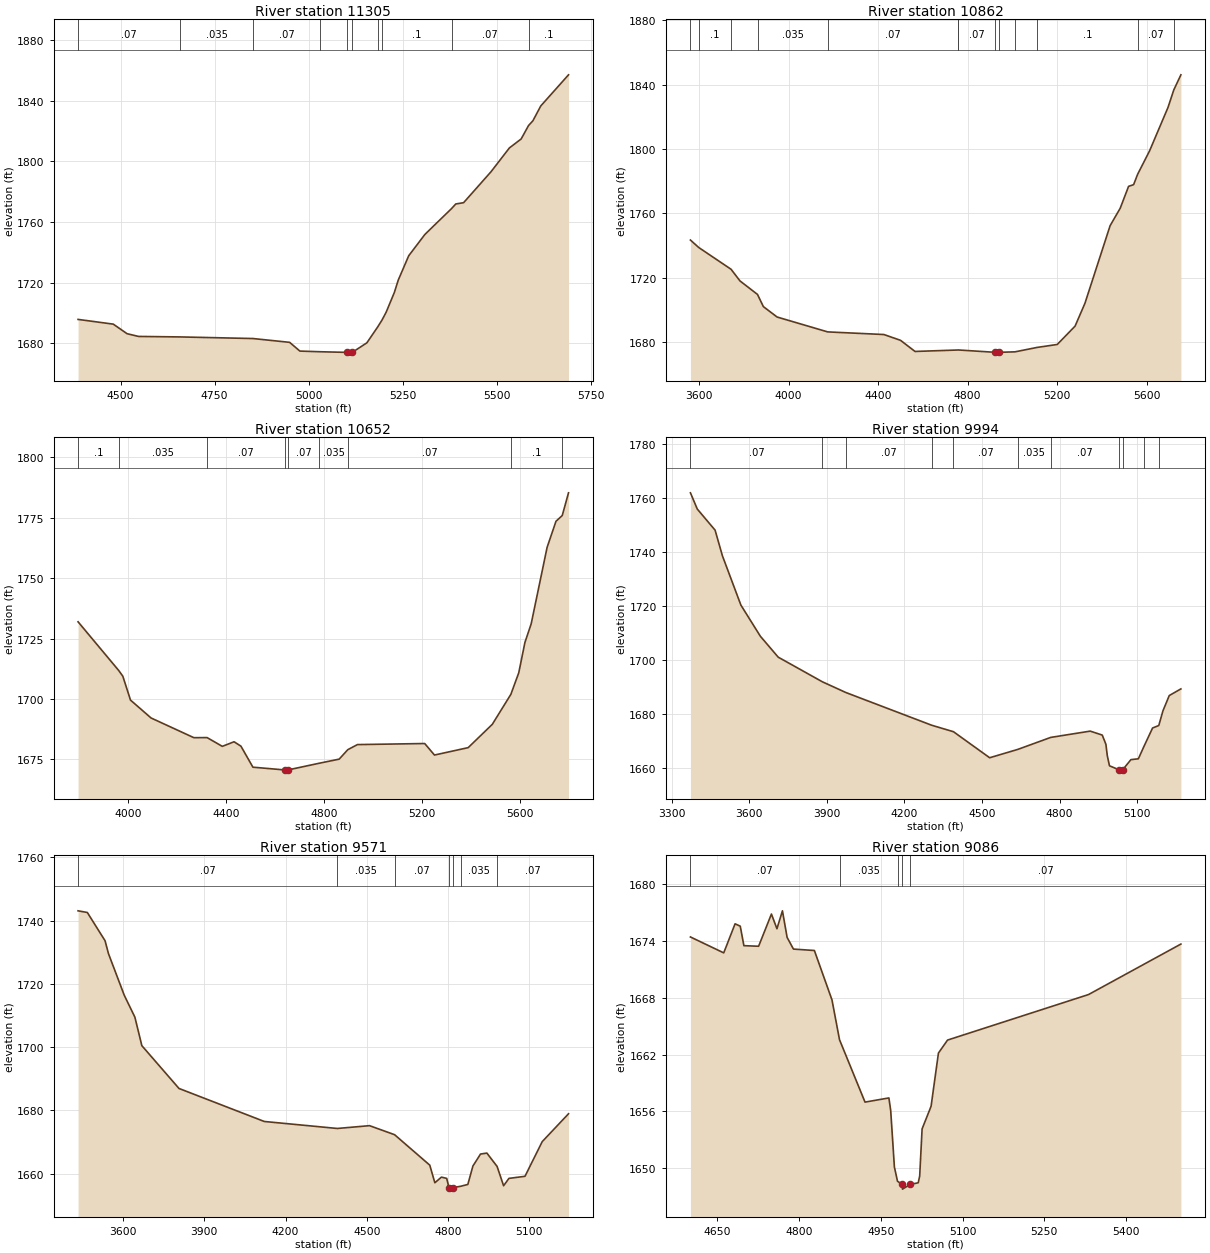
Type RM Length L Ch R = 1,11305,443,443,443
BEGIN DESCRIPTION:
Fall Creek 18.0
END DESCRIPTION:
XS GIS Cut Line= 3
      1916224.96     13888824.99      1916825.00     13888925.00
      1917424.97     13888575.02
#Sta/Elev= 30
  4387.1 1695.75  4480.7 1692.63  4517.2 1686.33  4547.6 1684.51  4658.9 1684.18
  4851.5 1683.13  4949.1 1680.61  4976.4 1674.84  5029.7 1674.40  5101.3 1673.99
  5101.8 1673.49  5115.5 1673.99  5154.3 1680.29  5183.1 1690.78  5194.5 1695.31
  5205.4 1700.41  5227.3 1713.52  5237.7 1721.70  5265.5 1737.78  5308.5 1751.86
  5379.7 1769.02  5390.5 1771.96  5411.3 1772.81  5484.3 1793.29  5532.9 1808.95
  5564.2 1814.88  5583.8 1823.74  5595.4 1826.89  5616.3 1836.68  5690.0 1857.22
#Mann=10,-1,0
  4387.1    0.07       0  4658.9   0.035       0  4851.5    0.07       0
  5029.7   0.033       0  5101.3    0.05       0  5115.5   0.033       0
  5183.1    0.07       0  5194.5     0.1       0  5379.7    0.07       0
  5583.8     0.1       0
Bank Sta=5101.3,5115.5
Exp/Cntr=0.3,0.1

Type RM Length L Ch R = 1,10862,210,210,210
BEGIN DESCRIPTION:
Fall Creek 17.0
END DESCRIPTION:
XS GIS Cut Line= 3
      1915875.00     13890075.00      1917075.00     13889275.00
      1917524.99     13888675.02
#Sta/Elev= 30
  3561.4 1743.49  3598.6 1738.86  3743.1 1725.34  3782.9 1718.12  3861.2 1709.73
  3887.4 1702.17  3948.7 1695.71  4174.9 1686.47  4426.1 1684.84  4500.4 1681.24
  4565.3 1674.33  4757.2 1675.23  4758.6 1675.25  4924.2 1673.79  4924.7 1673.29
  4938.4 1673.79  5012.4 1674.09  5111.4 1676.84  5201.0 1678.67  5280.7 1690.06
  5324.8 1704.26  5437.3 1752.43  5482.3 1763.23  5519.8 1776.83  5542.3 1777.89
  5560.2 1784.31  5613.5 1798.83  5696.0 1825.82  5721.8 1836.67  5753.6 1846.07
#Mann=13,-1,0
  3561.4    0.07       0  3598.6     0.1       0  3743.1    0.07       0
  3861.2   0.035       0  4174.9    0.07       0  4757.2   0.035       0
  4758.6    0.07       0  4924.2    0.05       0  4938.4    0.07       0
  5012.4   0.033       0  5111.4     0.1       0  5560.2    0.07       0
  5721.8     0.1       0
Bank Sta=4924.2,4938.4
Exp/Cntr=0.3,0.1

Type RM Length L Ch R = 1,10652,658,658,658
BEGIN DESCRIPTION:
Fall Creek 16.0
END DESCRIPTION:
XS GIS Cut Line= 4
      1916019.40     13890064.66      1916949.98     13889509.09
      1917231.23     13889377.15      1917571.48     13888873.71
#Sta/Elev= 30
  3797.3 1731.95  3963.2 1711.79  3980.0 1709.42  4011.4 1699.52  4095.3 1692.12
  4270.0 1683.96  4324.0 1684.00  4386.1 1680.37  4434.2 1682.27  4462.2 1680.44
  4511.1 1671.74  4640.2 1670.61  4640.7 1670.11  4654.4 1670.61  4782.4 1673.39
  4863.1 1675.07  4898.4 1678.99  4937.8 1681.10  5212.4 1681.54  5252.2 1676.77
  5389.8 1679.84  5488.3 1689.49  5564.0 1701.90  5596.2 1710.81  5621.5 1723.42
  5646.9 1731.07  5712.0 1762.79  5748.3 1773.59  5773.8 1775.96  5799.4 1785.36
#Mann=9,-1,0
  3797.3     0.1       0  3963.2   0.035       0  4324.0    0.07       0
  4640.2    0.05       0  4654.4    0.07       0  4782.4   0.035       0
  4898.4    0.07       0  5564.0     0.1       0  5773.8    0.07       0
Bank Sta=4640.2,4654.4
Exp/Cntr=0.3,0.1

Type RM Length L Ch R = 1,9994,423,423,423
BEGIN DESCRIPTION:
Fall Creek 15.0
END DESCRIPTION:
XS GIS Cut Line= 3
      1916174.98     13891025.02      1917375.00     13889925.00
      1917625.03     13889824.99
#Sta/Elev= 30
  3372.2 1762.01  3398.7 1756.00  3467.6 1748.17  3496.0 1738.64  3567.4 1720.39
  3642.6 1708.86  3711.7 1701.10  3882.6 1691.96  3973.6 1687.98  4305.5 1675.86
  4389.7 1673.46  4529.7 1663.81  4638.4 1666.90  4765.9 1671.35  4918.8 1673.68
  4965.2 1672.21  4979.3 1668.82  4984.7 1664.60  4993.2 1660.83  5029.8 1659.35
  5030.3 1658.85  5044.2 1659.35  5076.1 1663.11  5104.9 1663.42  5125.8 1667.86
  5159.8 1674.83  5183.9 1675.76  5200.0 1681.20  5224.4 1686.86  5269.4 1689.33
#Mann=11,-1,0
  3372.2    0.07       0  3882.6   0.035       0  3973.6    0.07       0
  4305.5     0.1       0  4389.7    0.07       0  4638.4   0.035       0
  4765.9    0.07       0  5029.8    0.05       0  5044.2    0.07       0
  5125.8     0.1       0  5183.9    0.07       0
Bank Sta=5029.8,5044.2
Exp/Cntr=0.3,0.1

Type RM Length L Ch R = 1,9571,485,485,485
BEGIN DESCRIPTION:
Fall Creek 14.0
END DESCRIPTION:
XS GIS Cut Line= 3
      1916375.03     13891274.98      1917575.00     13890275.00
      1917774.99     13890125.01
#Sta/Elev= 30
  3433.6 1743.07  3467.8 1742.55  3533.4 1733.60  3545.9 1729.54  3604.4 1716.35
  3643.5 1709.46  3669.3 1700.43  3806.5 1686.90  4121.7 1676.46  4391.7 1674.25
  4510.4 1675.14  4603.0 1672.28  4733.0 1662.65  4751.8 1657.08  4776.0 1658.86
  4795.5 1658.47  4803.9 1655.57  4804.4 1655.07  4818.3 1655.57  4846.8 1655.96
  4873.6 1656.55  4892.4 1662.38  4920.5 1666.16  4943.9 1666.47  4981.8 1662.24
  5005.7 1656.14  5025.5 1658.47  5084.7 1659.12  5148.5 1670.09  5245.6 1678.90
#Mann=7,-1,0
  3433.6    0.07       0  4391.7   0.035       0  4603.0    0.07       0
  4803.9    0.05       0  4818.3    0.07       0  4846.8   0.035       0
  4981.8    0.07       0
Bank Sta=4803.9,4818.3
Exp/Cntr=0.3,0.1

Type RM Length L Ch R = 1,9086,467,467,467
BEGIN DESCRIPTION:
Fall Creek 13.0
END DESCRIPTION:
XS GIS Cut Line= 4
      1917318.80     13890906.23      1917675.00     13890725.00
      1917790.23     13890665.84      1917928.44     13890321.96
#Sta/Elev= 30
  4600.8 1674.43  4661.9 1672.75  4682.7 1675.82  4692.2 1675.57  4698.9 1673.51
  4725.9 1673.45  4749.4 1676.85  4759.5 1675.30  4769.6 1677.19  4778.2 1674.38
  4789.8 1673.15  4828.2 1673.00  4860.5 1667.78  4874.3 1663.58  4921.1 1656.99
  4964.9 1657.43  4968.2 1656.12  4975.0 1650.13  4980.7 1648.63  4989.4 1648.30
  4989.9 1647.80  5004.1 1648.30  5018.7 1648.47  5021.4 1649.19  5025.8 1654.16
  5042.3 1656.55  5055.8 1662.17  5072.5 1663.54  5331.2 1668.35  5500.6 1673.68
#Mann=5,-1,0
  4600.8    0.07       0  4874.3   0.035       0  4980.7    0.07       0
  4989.4    0.05       0  5004.1    0.07       0
Bank Sta=4989.4,5004.1
Exp/Cntr=0.3,0.1

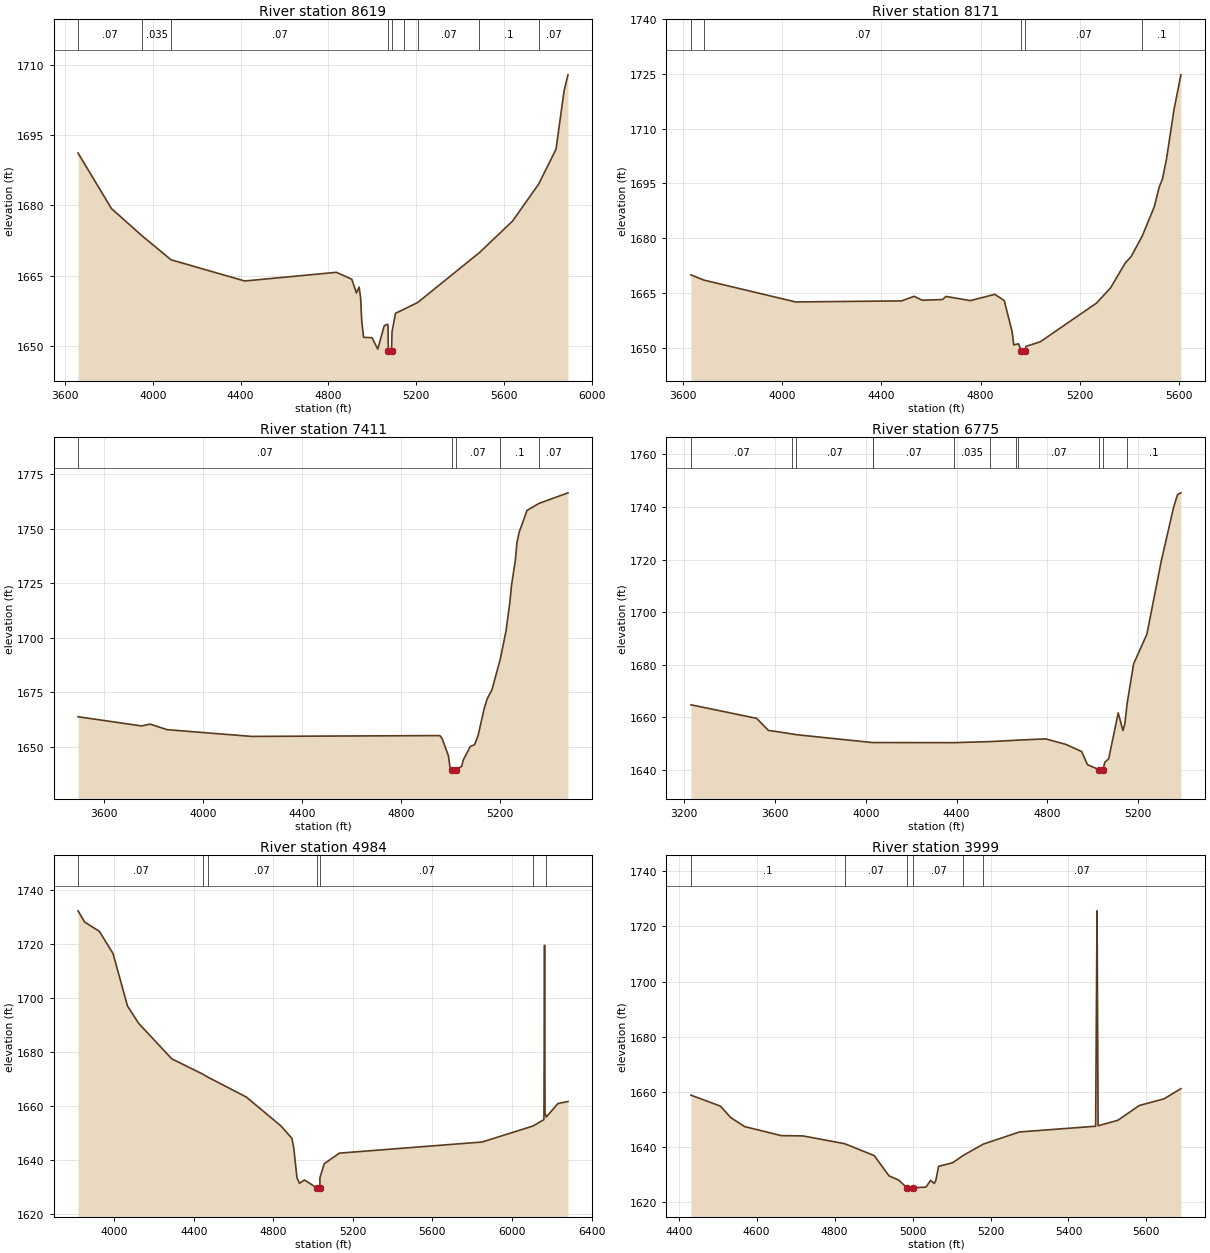
Type RM Length L Ch R = 1,8619,448,448,448
BEGIN DESCRIPTION:
Fall Creek 12.0
END DESCRIPTION:
XS GIS Cut Line= 3
      1916775.03     13891624.98      1917975.00     13891025.00
      1918647.35     13890440.34
#Sta/Elev= 30
  3659.5 1691.17  3811.8 1679.32  3952.6 1673.45  4083.6 1668.39  4418.9 1663.87
  4836.5 1665.72  4907.0 1664.25  4928.2 1661.30  4940.5 1662.57  4947.2 1660.27
  4952.2 1655.38  4960.7 1651.85  4999.2 1651.77  5025.3 1649.34  5054.5 1654.30
  5070.0 1654.65  5072.1 1654.29  5073.3 1648.98  5073.8 1648.48  5088.0 1648.98
  5090.2 1652.99  5106.1 1656.97  5145.7 1657.87  5207.2 1659.28  5488.4 1669.92
  5638.9 1676.62  5758.5 1684.54  5837.6 1691.98  5874.2 1704.42  5892.1 1707.85
#Mann=9,-1,0
  3659.5    0.07       0  3952.6   0.035       0  4083.6    0.07       0
  5073.3    0.05       0  5088.0    0.07       0  5145.7   0.035       0
  5207.2    0.07       0  5488.4     0.1       0  5758.5    0.07       0
Bank Sta=5073.3,5088
Exp/Cntr=0.3,0.1

Type RM Length L Ch R = 1,8171,760,760,760
BEGIN DESCRIPTION:
Fall Creek 11.0
END DESCRIPTION:
XS GIS Cut Line= 3
      1917080.77     13891640.60      1918375.00     13891175.00
      1918916.14     13890912.45
#Sta/Elev= 30
  3631.5 1669.92  3683.6 1668.49  4053.9 1662.50  4481.2 1662.79  4532.2 1664.05
  4564.1 1662.97  4646.9 1663.16  4660.1 1664.01  4758.5 1662.87  4857.4 1664.58
  4895.6 1662.87  4927.5 1654.29  4933.9 1650.73  4953.0 1651.03  4965.0 1648.97
  4965.5 1648.47  4980.3 1648.97  4982.6 1650.31  5040.6 1651.57  5267.3 1662.16
  5324.0 1666.30  5384.0 1673.20  5407.4 1674.93  5452.1 1680.53  5500.7 1688.55
  5520.7 1693.97  5534.1 1696.22  5550.7 1701.89  5580.8 1715.33  5608.4 1724.76
#Mann=5,-1,0
  3631.5   0.035       0  3683.6    0.07       0  4965.0    0.05       0
  4980.3    0.07       0  5452.1     0.1       0
Bank Sta=4965,4980.3
Exp/Cntr=0.3,0.1

Type RM Length L Ch R = 1,7411,636,636,636
BEGIN DESCRIPTION:
Fall Creek 10.1
END DESCRIPTION:
XS GIS Cut Line= 3
      1917377.33     13891631.66      1918756.05     13891695.64
      1919326.89     13891509.91
#Sta/Elev= 30
  3494.4 1663.85  3751.1 1659.64  3785.6 1660.48  3854.5 1657.93  4196.1 1654.84
  4956.9 1655.22  4966.3 1653.82  4991.6 1645.94  4997.9 1640.80  5005.9 1639.43
  5006.4 1638.93  5021.3 1639.43  5045.2 1641.17  5051.5 1644.01  5079.9 1650.20
  5097.4 1651.04  5111.4 1655.19  5136.7 1667.83  5148.5 1672.13  5167.5 1676.17
  5201.7 1690.49  5224.3 1703.10  5240.0 1716.30  5246.3 1723.76  5262.1 1735.48
  5268.4 1743.51  5277.9 1748.53  5309.4 1758.38  5357.0 1761.58  5474.9 1766.46
#Mann=5,-1,0
  3494.4    0.07       0  5005.9    0.05       0  5021.3    0.07       0
  5201.7     0.1       0  5357.0    0.07       0
Bank Sta=5005.9,5021.3
Exp/Cntr=0.3,0.1

Type RM Length L Ch R = 1,6775,1791,1791,1791
BEGIN DESCRIPTION:
Fall Creek 10.0
END DESCRIPTION:
XS GIS Cut Line= 3
      1917304.34     13891657.30      1918975.00     13892225.00
      1919366.92     13892197.07
#Sta/Elev= 30
  3230.3 1664.78  3519.4 1659.63  3571.4 1655.05  3674.7 1653.71  3692.0 1653.44
  4031.8 1650.41  4033.1 1650.43  4388.0 1650.39  4549.2 1650.80  4660.0 1651.29
  4670.8 1651.36  4792.3 1651.82  4881.0 1649.74  4950.7 1647.01  4976.1 1642.03
  5028.7 1640.07  5029.2 1639.57  5044.1 1640.07  5053.1 1643.01  5069.5 1644.24
  5111.6 1661.69  5132.7 1655.00  5140.6 1657.43  5151.4 1665.58  5179.4 1680.32
  5237.9 1691.62  5301.1 1719.39  5355.2 1739.75  5372.9 1744.68  5387.7 1745.34
#Mann=12,-1,0
  3230.3    0.07       0  3674.7     0.1       0  3692.0    0.07       0
  4031.8     0.1       0  4033.1    0.07       0  4388.0   0.035       0
  4549.2    0.07       0  4660.0   0.035       0  4670.8    0.07       0
  5028.7    0.05       0  5044.1    0.07       0  5151.4     0.1       0
Bank Sta=5028.7,5044.1
Exp/Cntr=0.3,0.1

Type RM Length L Ch R = 1,4984,985,985,985
BEGIN DESCRIPTION:
Fall Creek 9.0
END DESCRIPTION:
XS GIS Cut Line= 3
      1916752.17     13893177.13      1917875.00     13892825.00
      1919129.12     13892538.87
#Sta/Elev= 30
  3818.6 1732.26  3852.1 1728.10  3925.6 1724.69  3994.8 1716.42  4067.1 1697.06
  4123.7 1690.58  4290.3 1677.46  4447.0 1671.76  4470.6 1670.74  4664.5 1663.34
  4837.4 1652.73  4894.0 1648.04  4903.4 1644.36  4919.1 1633.51  4931.7 1631.39
  4956.9 1632.63  5018.3 1629.75  5018.8 1629.25  5034.5 1629.75  5034.6 1633.43
  5056.1 1638.64  5132.5 1642.57  5850.0 1646.69  6105.3 1652.60  6160.8 1654.97
  6163.9 1719.54  6166.2 1657.34  6172.6 1655.94  6230.9 1660.92  6281.7 1661.70
#Mann=7,-1,0
  3818.6    0.07       0  4447.0   0.035       0  4470.6    0.07       0
  5018.3    0.05       0  5034.5    0.07       0  6105.3     0.1       0
  6172.6    0.07       0
Bank Sta=5018.3,5034.5
Exp/Cntr=0.3,0.1

Type RM Length L Ch R = 1,3999,333,333,333
BEGIN DESCRIPTION:
Fall Creek 8.0
END DESCRIPTION:
XS GIS Cut Line= 3
      1918225.03     13893424.97      1918641.46     13893000.23
      1919193.72     13892634.52
#Sta/Elev= 30
  4431.4 1658.83  4506.9 1654.84  4533.3 1650.71  4568.9 1647.43  4663.1 1644.15
  4718.9 1644.04  4825.9 1641.22  4901.8 1636.88  4939.6 1629.56  4964.8 1627.98
  4985.5 1625.24  4986.0 1624.74  5001.8 1625.24  5034.4 1625.47  5046.3 1627.89
  5056.0 1626.81  5059.6 1627.85  5066.8 1633.01  5102.8 1634.30  5130.4 1637.00
  5181.6 1641.07  5274.4 1645.48  5469.8 1647.55  5472.4 1705.07  5473.4 1725.68
  5476.1 1647.72  5526.5 1649.69  5581.8 1655.07  5645.2 1657.49  5688.6 1661.18
#Mann=6,-1,0
  4431.4     0.1       0  4825.9    0.07       0  4985.5    0.05       0
  5001.8    0.07       0  5130.4     0.1       0  5181.6    0.07       0
Bank Sta=4985.5,5001.8
Exp/Cntr=0.3,0.1

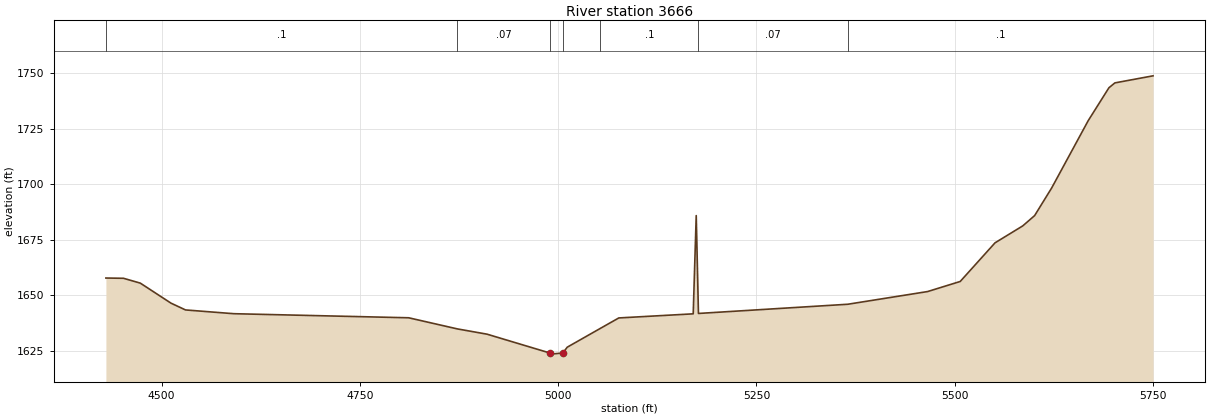
Type RM Length L Ch R = 1,3666,422,422,422
BEGIN DESCRIPTION:
Fall Creek 7.0
END DESCRIPTION:
XS GIS Cut Line= 3
      1918425.01     13893574.99      1918875.00     13893225.00
      1919475.02     13892774.99
#Sta/Elev= 30
  4429.9 1657.86  4452.1 1657.74  4473.3 1655.56  4512.0 1646.54  4530.3 1643.49
  4591.1 1641.80  4811.6 1639.96  4872.9 1634.96  4910.4 1632.58  4989.6 1624.10
  4990.1 1623.60  5005.9 1624.10  5011.5 1626.72  5053.1 1635.16  5076.5 1639.89
  5170.3 1641.74  5174.1 1685.95  5176.7 1645.06  5176.9 1641.91  5365.1 1646.05
  5465.8 1651.77  5506.9 1656.31  5550.8 1673.71  5585.7 1681.32  5600.7 1685.96
  5622.2 1698.41  5668.2 1728.67  5694.4 1743.53  5701.9 1745.71  5750.0 1748.89
#Mann=7,-1,0
  4429.9     0.1       0  4872.9    0.07       0  4989.6    0.05       0
  5005.9    0.07       0  5053.1     0.1       0  5176.7    0.07       0
  5365.1     0.1       0
Bank Sta=4989.6,5005.9
Exp/Cntr=0.3,0.1