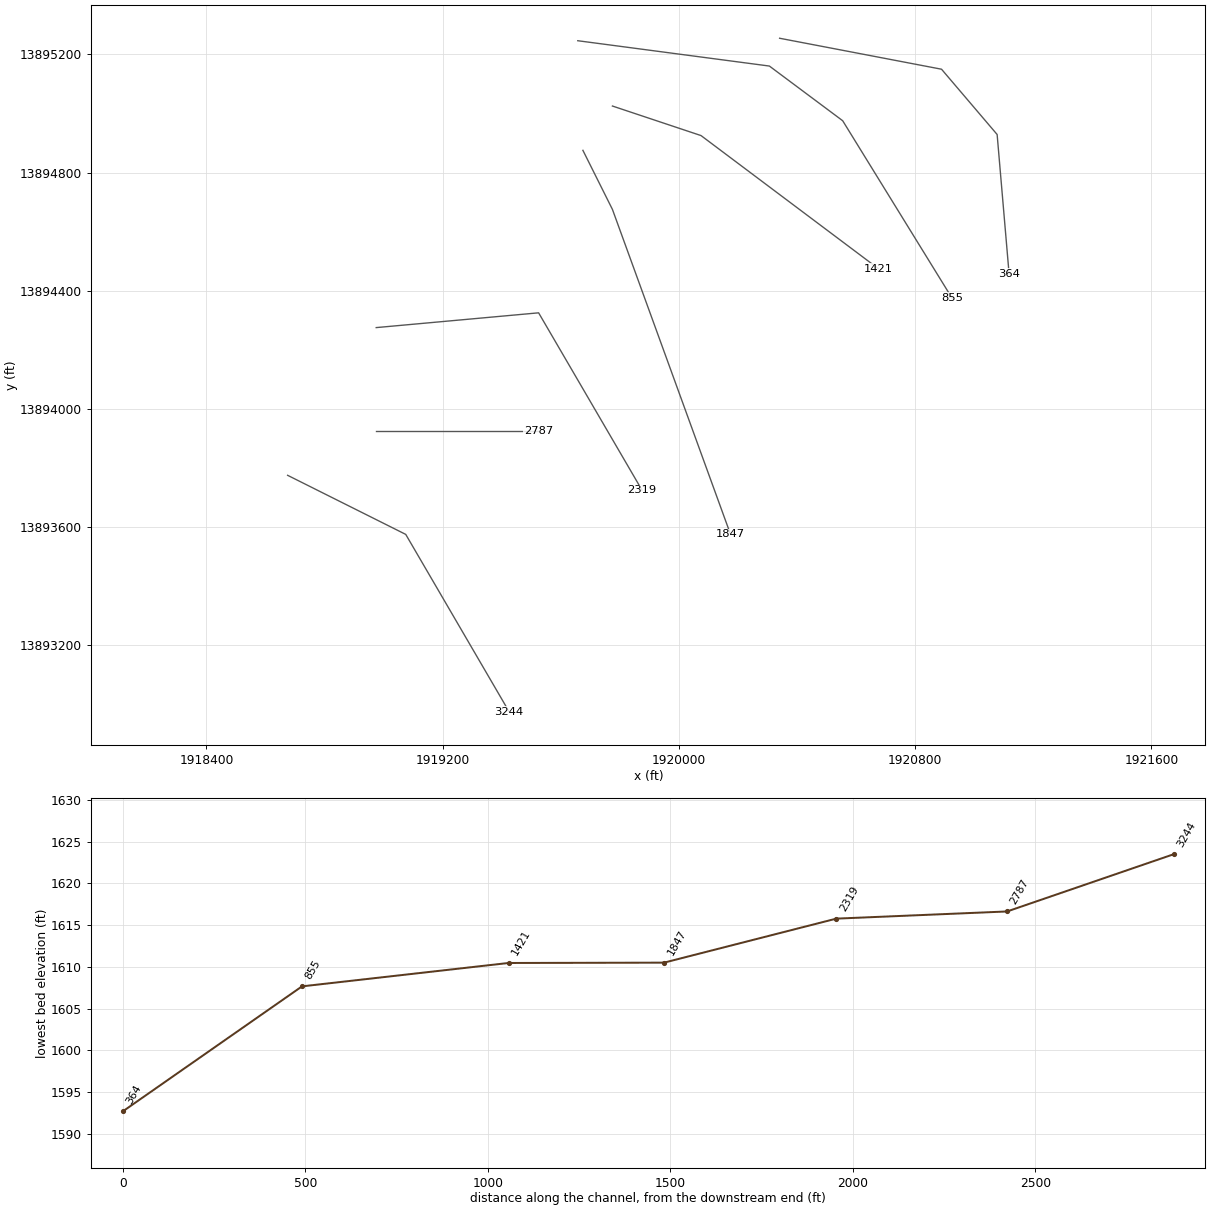
HEC-RAS study Fall Creek.prj: Fall Creek Base Level Engineering

--- Fall Creek.g01 (geometry) --- (continued)

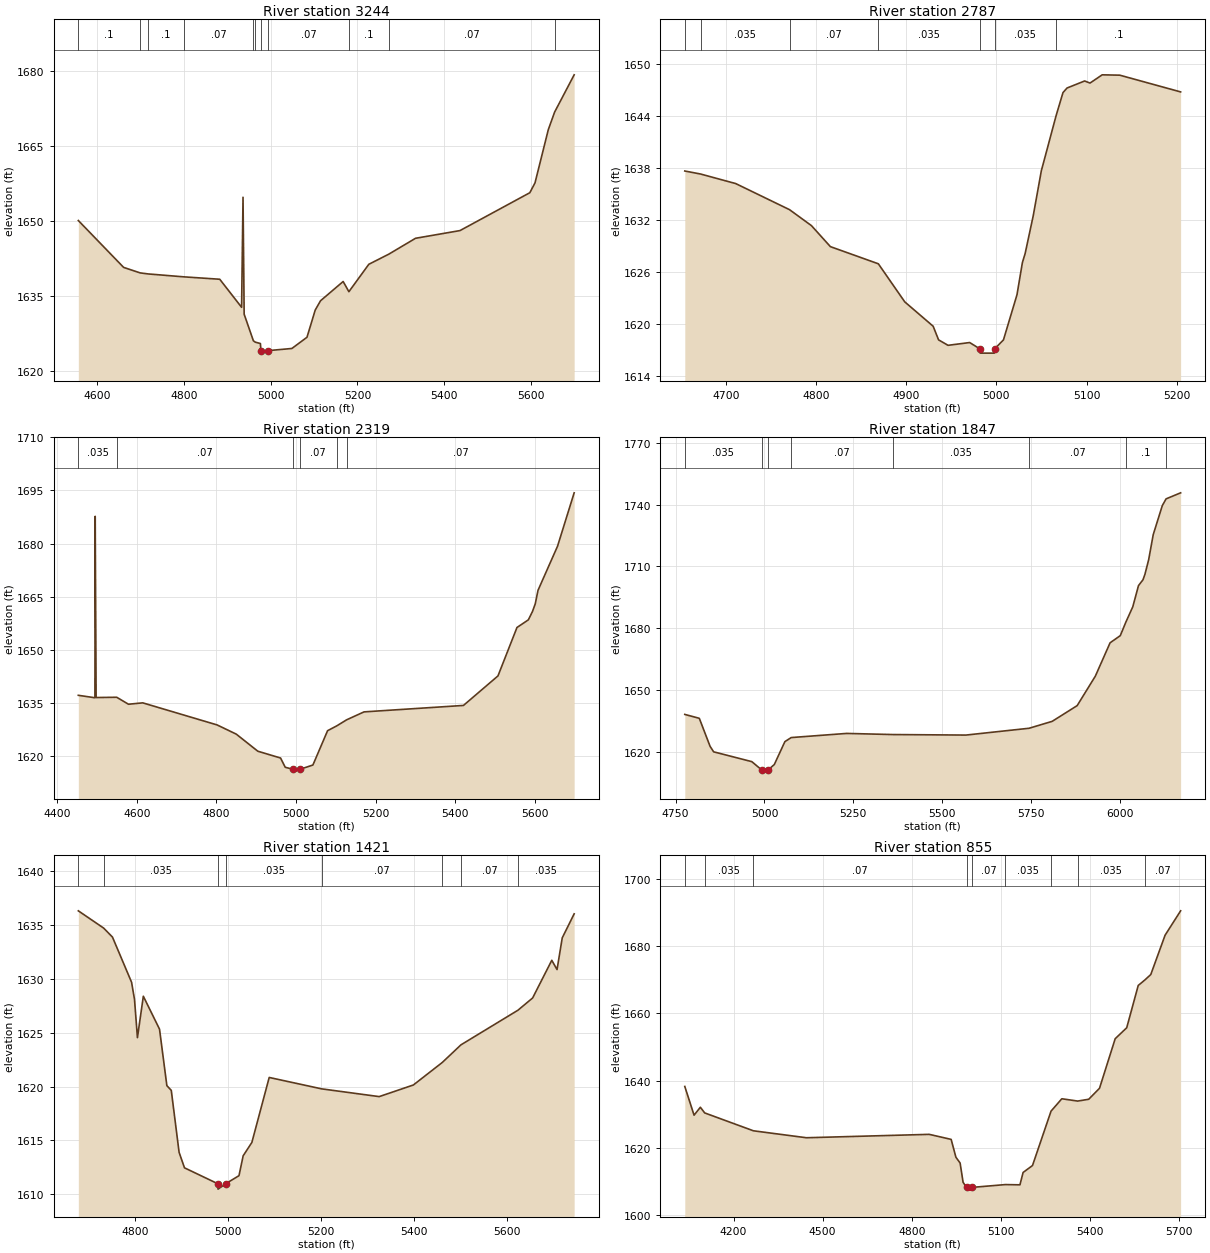
Type RM Length L Ch R = 1,3244,457,457,457
BEGIN DESCRIPTION:
Fall Creek 6.0
END DESCRIPTION:
XS GIS Cut Line= 3
      1918674.98     13893775.01      1919075.00     13893575.00
      1919425.02     13892974.97
#Sta/Elev= 30
  4557.3 1650.01  4661.6 1640.64  4699.7 1639.54  4718.5 1639.33  4800.3 1638.75
  4883.0 1638.27  4933.3 1632.66  4936.6 1654.66  4939.2 1631.28  4960.5 1625.96
  4965.0 1625.69  4976.6 1625.42  4977.9 1624.00  4978.4 1623.50  4994.3 1624.00
  5049.1 1624.43  5083.9 1626.67  5102.9 1632.12  5115.1 1633.97  5167.2 1637.82
  5180.4 1635.78  5226.3 1641.26  5272.6 1643.30  5333.9 1646.46  5436.3 1648.00
  5597.1 1655.57  5609.0 1657.53  5639.6 1668.16  5654.2 1671.69  5699.2 1679.14
#Mann=11,-1,0
  4557.3     0.1       0  4699.7    0.07       0  4718.5     0.1       0
  4800.3    0.07       0  4960.5   0.035       0  4965.0    0.07       0
  4977.9    0.05       0  4994.3    0.07       0  5180.4     0.1       0
  5272.6    0.07       0  5654.2     0.1       0
Bank Sta=4977.9,4994.3
Exp/Cntr=0.3,0.1

Type RM Length L Ch R = 1,2787,468,468,468
BEGIN DESCRIPTION:
Fall Creek 5.0
END DESCRIPTION:
XS GIS Cut Line= 3
      1918975.05     13893925.00      1919325.00     13893925.00
      1919525.05     13893925.00
#Sta/Elev= 30
  4654.4 1637.64  4672.0 1637.29  4710.9 1636.19  4770.6 1633.18  4794.9 1631.34
  4815.9 1628.92  4869.1 1626.94  4898.4 1622.55  4929.9 1619.74  4935.9 1618.17
  4946.4 1617.54  4970.4 1617.86  4981.6 1617.14  4982.1 1616.64  4997.7 1616.64
  4998.2 1617.14  5007.9 1618.17  5022.9 1623.38  5028.9 1627.09  5031.9 1628.11
  5040.9 1632.48  5049.9 1637.67  5066.3 1644.03  5073.9 1646.68  5078.4 1647.21
  5097.9 1648.02  5103.9 1647.78  5117.4 1648.73  5136.9 1648.69  5204.4 1646.76
#Mann=7,-1,0
  4654.4    0.07       0  4672.0   0.035       0  4770.6    0.07       0
  4869.1   0.035       0  4981.6   0.035       0  4998.2   0.035       0
  5066.3     0.1       0
Bank Sta=4981.6,4998.2
Exp/Cntr=0.3,0.1

Type RM Length L Ch R = 1,2319,472,472,472
BEGIN DESCRIPTION:
Fall Creek 4.0
END DESCRIPTION:
XS GIS Cut Line= 3
      1918975.01     13894275.00      1919525.00     13894325.00
      1919875.01     13893724.98
#Sta/Elev= 30
  4452.6 1637.18  4494.3 1636.49  4494.7 1662.41  4495.0 1687.69  4497.3 1636.55
  4549.1 1636.63  4578.7 1634.66  4614.6 1635.05  4801.6 1628.82  4849.8 1626.22
  4904.0 1621.40  4961.2 1619.48  4972.9 1616.87  4992.9 1616.28  4993.4 1615.78
  5009.6 1616.28  5042.5 1617.50  5079.4 1627.19  5102.0 1628.52  5127.3 1630.26
  5171.0 1632.50  5421.1 1634.32  5507.9 1642.65  5555.7 1656.32  5584.3 1658.48
  5594.7 1660.84  5601.7 1663.00  5608.6 1666.81  5657.7 1679.26  5699.5 1694.33
#Mann=6,-1,0
  4452.6   0.035       0  4549.1    0.07       0  4992.9    0.05       0
  5009.6    0.07       0  5102.0     0.1       0  5127.3    0.07       0
Bank Sta=4992.9,5009.6
Exp/Cntr=0.3,0.1

Type RM Length L Ch R = 1,1847,426,426,426
BEGIN DESCRIPTION:
Fall Creek 3.0
END DESCRIPTION:
XS GIS Cut Line= 3
      1919674.99     13894875.03      1919775.00     13894675.00
      1920174.96     13893575.10
#Sta/Elev= 30
  4776.1 1638.07  4816.9 1636.18  4847.1 1622.60  4857.2 1619.89  4964.5 1615.12
  4992.9 1611.01  4993.4 1610.51  5009.7 1611.01  5027.7 1613.70  5057.5 1624.84
  5075.2 1626.82  5231.2 1628.83  5362.0 1628.28  5566.4 1628.03  5744.0 1631.34
  5809.0 1634.70  5879.2 1642.34  5930.3 1656.65  5971.8 1672.87  6000.5 1676.36
  6015.8 1682.79  6035.6 1690.36  6051.6 1700.64  6064.3 1703.50  6069.8 1706.17
  6080.3 1713.29  6093.1 1725.45  6118.6 1739.53  6129.2 1742.81  6170.1 1745.75
#Mann=8,-1,0
  4776.1   0.035       0  4992.9   0.035       0  5009.7   0.035       0
  5075.2    0.07       0  5362.0   0.035       0  5744.0    0.07       0
  6015.8     0.1       0  6129.2    0.07       0
Bank Sta=4992.9,5009.7
Exp/Cntr=0.3,0.1

Type RM Length L Ch R = 1,1421,566,566,566
BEGIN DESCRIPTION:
Fall Creek 2.0
END DESCRIPTION:
XS GIS Cut Line= 3
      1919774.96     13895025.01      1920075.00     13894925.00
      1920675.02     13894474.98
#Sta/Elev= 30
  4678.2 1636.34  4732.5 1634.74  4751.6 1633.90  4792.7 1629.70  4799.0 1628.11
  4805.3 1624.55  4818.0 1628.40  4852.8 1625.34  4868.6 1620.09  4878.1 1619.65
  4894.9 1613.89  4906.5 1612.45  4978.2 1610.97  4978.7 1610.47  4995.0 1610.97
  5023.7 1611.72  5032.7 1613.57  5051.4 1614.81  5088.7 1620.85  5201.5 1619.79
  5325.2 1619.07  5398.7 1620.15  5460.8 1622.24  5501.0 1623.88  5623.6 1627.10
  5655.2 1628.24  5696.4 1631.74  5707.7 1630.88  5718.9 1633.83  5744.5 1636.06
#Mann=8,-1,0
  4678.2    0.07       0  4732.5   0.035       0  4978.2   0.035       0
  4995.0   0.035       0  5201.5    0.07       0  5460.8   0.035       0
  5501.0    0.07       0  5623.6   0.035       0
Bank Sta=4978.2,4995
Exp/Cntr=0.3,0.1

Type RM Length L Ch R = 1,855,491,491,491
BEGIN DESCRIPTION:
Fall Creek 1.0
END DESCRIPTION:
XS GIS Cut Line= 4
      1919657.61     13895246.06      1920306.55     13895160.32
      1920554.75     13894975.23      1920924.99     13894375.02
#Sta/Elev= 30
  4036.0 1638.24  4067.2 1629.69  4088.4 1632.05  4103.0 1630.36  4267.0 1625.04
  4445.5 1622.97  4859.0 1623.98  4932.8 1622.48  4948.8 1617.17  4963.0 1615.43
  4973.0 1609.70  4984.6 1608.17  4985.1 1607.67  5001.5 1608.17  5115.0 1609.02
  5164.4 1608.95  5175.0 1612.63  5206.7 1614.70  5269.1 1630.89  5305.4 1634.58
  5358.7 1633.89  5396.0 1634.43  5432.3 1637.70  5485.1 1652.46  5523.9 1655.72
  5562.7 1668.32  5585.0 1669.95  5605.0 1671.58  5653.1 1683.28  5705.4 1690.54
#Mann=9,-1,0
  4036.0    0.07       0  4103.0   0.035       0  4267.0    0.07       0
  4984.6    0.05       0  5001.5    0.07       0  5115.0   0.035       0
  5269.1    0.07       0  5358.7   0.035       0  5585.0    0.07       0
Bank Sta=4984.6,5001.5
Exp/Cntr=0.3,0.1

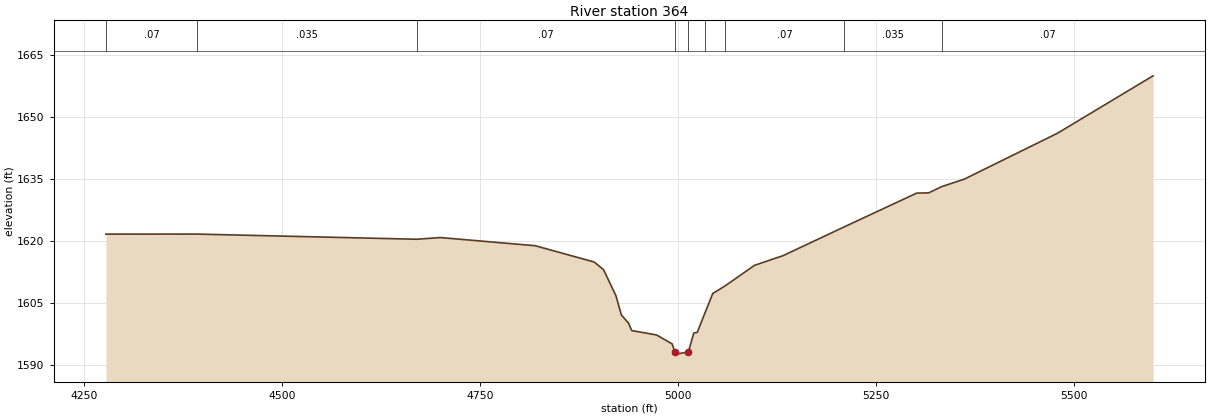
Type RM Length L Ch R = 1,364,0,0,0
BEGIN DESCRIPTION:
Fall Creek 0.0
END DESCRIPTION:
XS GIS Cut Line= 4
      1920341.17     13895254.42      1920889.51     13895149.62
      1921077.83     13894928.63      1921118.29     13894457.28
#Sta/Elev= 30
  4277.6 1621.74  4392.5 1621.75  4670.1 1620.50  4699.8 1620.91  4819.6 1618.93
  4893.9 1614.99  4905.7 1613.14  4921.4 1606.83  4928.2 1602.19  4937.2 1600.21
  4941.2 1598.41  4972.7 1597.33  4992.4 1595.16  4995.7 1593.20  4996.2 1592.70
  5012.7 1593.20  5019.7 1597.83  5024.0 1597.97  5034.3 1602.93  5043.6 1607.38
  5058.7 1609.15  5096.3 1614.19  5132.4 1616.54  5209.7 1623.51  5301.0 1631.67
  5316.1 1631.73  5333.0 1633.27  5361.2 1635.06  5478.6 1646.15  5599.3 1660.05
#Mann=9,-1,0
  4277.6    0.07       0  4392.5   0.035       0  4670.1    0.07       0
  4995.7    0.05       0  5012.7    0.07       0  5034.3   0.035       0
  5058.7    0.07       0  5209.7   0.035       0  5333.0    0.07       0
Bank Sta=4995.7,5012.7
Exp/Cntr=0.3,0.1

Chan Stop Cuts=-1