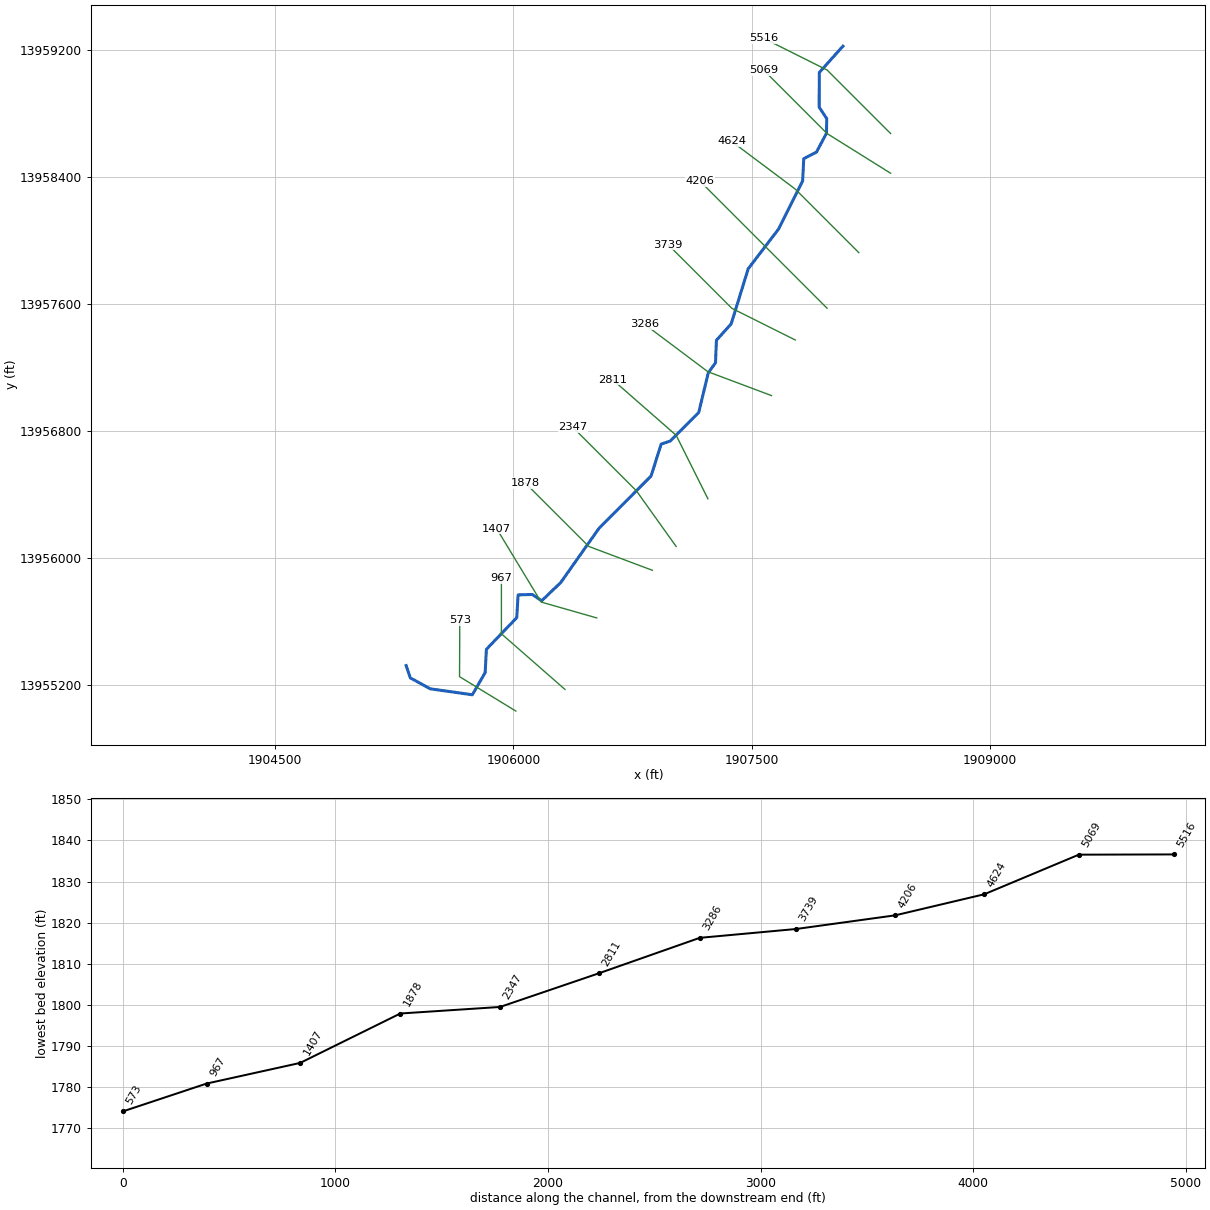
--- George Hollow.prj (project) ---

Proj Title=George Hollow Base Level Engineering
Current Plan=p01
Default Exp/Contr=0.3,0.1
English Units
Geom File=g01
Flow File=f01
Plan File=p01
BEGIN DESCRIPTION:
George Hollow
END DESCRIPTION:

--- George Hollow.p01 (plan) ---

Plan Title=Multiple Run
Short Identifier=Multiple
Geom File=g01
Flow File=f01
Subcritical Flow
K Sum by GR= 0
Std Step Tol= 0.01
Critical Tol= 0.01
Num of Std Step Trials= 20
Max Error Tol= 0.3
Flow Tol Ratio= 0.001
Split Flow NTrial= 30
Split Flow Tol= 0.02
Split Flow Ratio= 0.02
Log Output Level= 0
Friction Slope Method= 1
Unsteady Friction Slope Method= 2
Unsteady Bridges Friction Slope Method= 1
Parabolic Critical Depth
Global Vel Dist=  1 , 1 , 1
Global Log Level= 0
CheckData=True
Encroach Param= -1, 0, 0, 0
BEGIN DESCRIPTION:
Multiple Run
END DESCRIPTION:

--- George Hollow.f01 (steady flow) ---

Flow Title=Multiple
Number of Profiles=7
Profile Names=10-year,25-year,50-year,1pct_min,100-year,1pct_plu,500-year
River Rch & RM= George Hollow,Reach-1,5516
    1824    3204    4553    3122    6230   12430   11531
Boundary for River Rch & Prof#=George Hollow,Reach-1,1
Up Type=0
Dn Type=3
Dn Slope=0.005
Boundary for River Rch & Prof#=George Hollow,Reach-1,2
Up Type=0
Dn Type=3
Dn Slope=0.005
Boundary for River Rch & Prof#=George Hollow,Reach-1,3
Up Type=0
Dn Type=3
Dn Slope=0.005
Boundary for River Rch & Prof#=George Hollow,Reach-1,4
Up Type=0
Dn Type=3
Dn Slope=0.005
Boundary for River Rch & Prof#=George Hollow,Reach-1,5
Up Type=0
Dn Type=3
Dn Slope=0.005
Boundary for River Rch & Prof#=George Hollow,Reach-1,6
Up Type=0
Dn Type=3
Dn Slope=0.005
Boundary for River Rch & Prof#=George Hollow,Reach-1,7
Up Type=0
Dn Type=3
Dn Slope=0.005

--- George Hollow.g01 (geometry) ---

Geom Title=Existing Conditions

River Reach=George Hollow,Reach-1
Reach XY= 30
      1908075.00     13959225.00      1907925.92     13959059.06
      1907925.52     13958840.22      1907972.83     13958769.02
      1907971.33     13958676.58      1907908.43     13958557.98
      1907828.10     13958516.69      1907821.24     13958376.56
      1907669.15     13958072.71      1907478.62     13957823.50
      1907371.38     13957476.50      1907278.56     13957373.53
      1907272.73     13957230.94      1907227.36     13957169.02
      1907167.14     13956918.83      1906987.98     13956738.73
      1906930.59     13956719.39      1906867.14     13956518.83
      1906538.63     13956188.21      1906298.70     13955848.18
      1906178.42     13955732.80      1906119.01     13955772.67
      1906030.04     13955770.07      1906021.45     13955626.48
      1905830.47     13955427.45      1905822.75     13955280.93
      1905742.09     13955141.14      1905476.55     13955178.75
      1905351.15     13955247.72      1905325.00     13955325.00

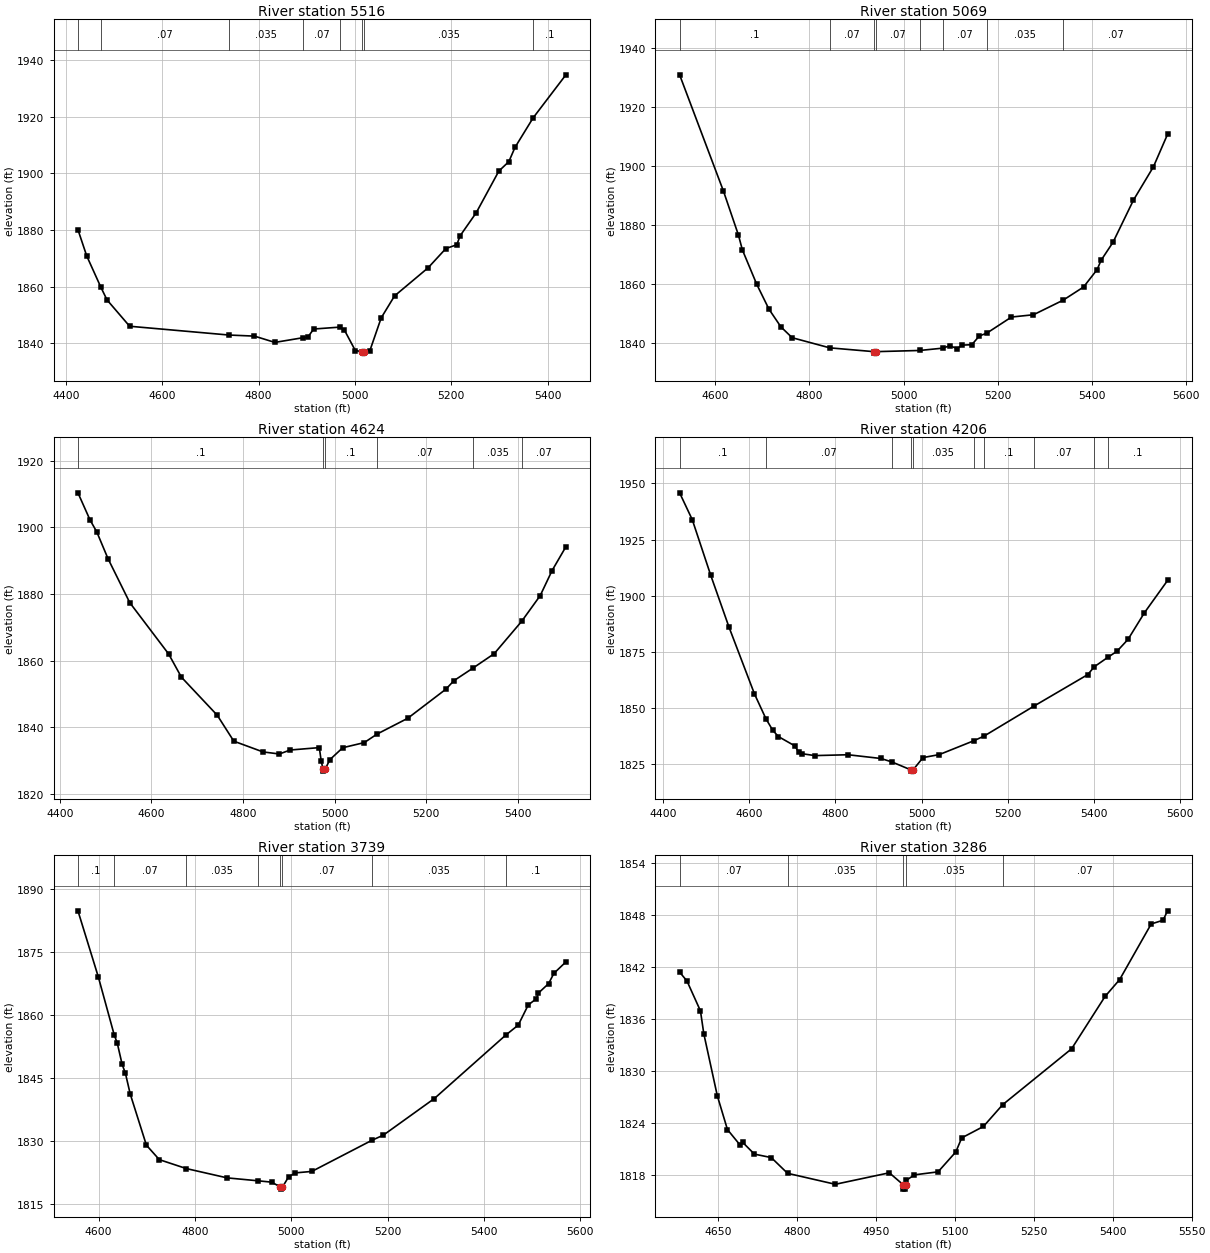
Type RM Length L Ch R = 1,5516,447,447,447
BEGIN DESCRIPTION:
Stream0465 11.0
END DESCRIPTION:
XS GIS Cut Line= 3
      1908374.98     13958675.02      1907975.00     13959075.00
      1907574.98     13959275.01
#Sta/Elev= 30
  4425.0 1880.14  4443.2 1870.89  4472.8 1859.76  4485.4 1855.36  4532.3 1846.08
  4738.6 1842.98  4791.4 1842.60  4833.8 1840.38  4892.9 1842.06  4901.7 1842.13
  4914.4 1845.10  4968.4 1845.77  4978.1 1844.74  5000.8 1837.51  5015.6 1837.10
  5015.9 1836.60  5019.6 1837.10  5031.0 1837.47  5054.5 1849.03  5082.2 1856.77
  5151.8 1866.68  5188.7 1873.47  5211.5 1874.83  5218.2 1877.95  5251.7 1886.09
  5298.7 1900.80  5319.5 1904.14  5332.2 1909.14  5370.0 1919.60  5437.9 1934.75
#Mann=8,-1,0
  4425.0     0.1       0  4472.8    0.07       0  4738.6   0.035       0
  4892.9    0.07       0  4968.4   0.035       0  5015.6   0.035       0
  5019.6   0.035       0  5370.0     0.1       0
Bank Sta=5015.6,5019.6
Exp/Cntr=0.3,0.1

Type RM Length L Ch R = 1,5069,445,445,445
BEGIN DESCRIPTION:
Stream0465 10.0
END DESCRIPTION:
XS GIS Cut Line= 3
      1908374.98     13958425.02      1907975.00     13958675.00
      1907574.97     13959075.03
#Sta/Elev= 30
  4523.9 1930.83  4617.2 1891.40  4649.0 1876.52  4657.3 1871.54  4687.9 1859.85
  4713.9 1851.42  4739.3 1845.43  4763.2 1841.76  4843.1 1838.33  4937.0 1837.04
  4937.3 1836.54  4941.1 1837.04  5034.4 1837.44  5082.9 1838.22  5098.4 1839.03
  5114.5 1838.05  5123.9 1839.25  5145.1 1839.39  5161.2 1842.37  5176.7 1843.28
  5229.5 1848.77  5276.2 1849.54  5339.3 1854.48  5382.7 1858.94  5411.5 1864.83
  5420.0 1868.00  5445.4 1874.12  5488.8 1888.39  5531.2 1899.66  5561.3 1910.69
#Mann=8,-1,0
  4523.9     0.1       0  4843.1    0.07       0  4937.0    0.05       0
  4941.1    0.07       0  5034.4   0.035       0  5082.9    0.07       0
  5176.7   0.035       0  5339.3    0.07       0
Bank Sta=4937,4941.1
Exp/Cntr=0.3,0.1

Type RM Length L Ch R = 1,4624,418,418,418
BEGIN DESCRIPTION:
Stream0465 9.0
END DESCRIPTION:
XS GIS Cut Line= 3
      1908174.97     13957925.03      1907775.00     13958325.00
      1907375.04     13958624.97
#Sta/Elev= 30
  4439.4 1910.35  4465.9 1902.19  4480.5 1898.65  4505.0 1890.63  4552.6 1877.42
  4637.5 1862.03  4665.3 1855.09  4743.6 1843.67  4779.8 1835.89  4843.5 1832.67
  4879.3 1832.05  4902.9 1833.24  4966.5 1833.96  4970.7 1829.88  4974.9 1827.41
  4975.1 1826.91  4979.0 1827.41  4989.6 1830.35  5017.7 1833.93  5064.6 1835.46
  5093.0 1838.05  5159.6 1842.75  5242.7 1851.45  5260.6 1854.04  5302.8 1857.87
  5348.5 1862.13  5408.3 1871.80  5448.9 1879.53  5474.9 1887.06  5505.0 1894.18
#Mann=6,-1,0
  4439.4     0.1       0  4974.9    0.05       0  4979.0     0.1       0
  5093.0    0.07       0  5302.8   0.035       0  5408.3    0.07       0
Bank Sta=4974.9,4979
Exp/Cntr=0.3,0.1

Type RM Length L Ch R = 1,4206,467,467,467
BEGIN DESCRIPTION:
Stream0465 8.0
END DESCRIPTION:
XS GIS Cut Line= 3
      1907975.03     13957574.97      1907575.00     13957975.00
      1907175.00     13958375.00
#Sta/Elev= 30
  4439.1 1945.82  4468.5 1933.83  4511.4 1909.00  4553.8 1885.87  4612.7 1856.19
  4639.6 1845.00  4655.1 1840.00  4668.1 1837.21  4706.1 1833.06  4715.0 1830.37
  4723.0 1829.56  4752.7 1828.72  4829.6 1829.10  4906.0 1827.43  4931.9 1825.85
  4976.0 1822.30  4976.2 1821.80  4980.2 1822.30  5003.5 1827.84  5041.2 1829.17
  5120.9 1835.31  5145.1 1837.42  5259.7 1850.66  5385.4 1864.81  5400.6 1868.31
  5433.2 1872.67  5453.3 1875.23  5478.7 1880.48  5516.9 1892.39  5570.5 1906.76
#Mann=10,-1,0
  4439.1     0.1       0  4639.6    0.07       0  4931.9   0.035       0
  4976.0   0.035       0  4980.2   0.035       0  5120.9    0.07       0
  5145.1     0.1       0  5259.7    0.07       0  5400.6   0.035       0
  5433.2     0.1       0
Bank Sta=4976,4980.2
Exp/Cntr=0.3,0.1

Type RM Length L Ch R = 1,3739,453,453,453
BEGIN DESCRIPTION:
Stream0465 7.0
END DESCRIPTION:
XS GIS Cut Line= 3
      1907774.96     13957375.02      1907375.00     13957575.00
      1906974.97     13957975.03
#Sta/Elev= 30
  4557.0 1884.81  4599.3 1869.06  4632.1 1855.32  4638.7 1853.24  4648.8 1848.18
  4655.5 1846.11  4665.5 1841.16  4699.1 1828.95  4725.9 1825.50  4782.0 1823.37
  4866.8 1821.15  4930.5 1820.46  4959.3 1820.13  4977.3 1818.97  4977.6 1818.47
  4981.6 1818.97  4994.2 1821.37  5008.0 1822.34  5042.5 1822.69  5166.7 1830.08
  5191.0 1831.34  5296.8 1840.06  5444.8 1855.16  5471.0 1857.57  5491.7 1862.36
  5508.7 1863.87  5512.9 1865.21  5534.1 1867.47  5545.0 1869.91  5569.9 1872.63
#Mann=8,-1,0
  4557.0     0.1       0  4632.1    0.07       0  4782.0   0.035       0
  4930.5    0.07       0  4977.3    0.05       0  4981.6    0.07       0
  5166.7   0.035       0  5444.8     0.1       0
Bank Sta=4977.3,4981.6
Exp/Cntr=0.3,0.1

Type RM Length L Ch R = 1,3286,475,475,475
BEGIN DESCRIPTION:
Stream0465 6.0
END DESCRIPTION:
XS GIS Cut Line= 3
      1907624.99     13957025.00      1907225.00     13957175.00
      1906824.99     13957475.01
#Sta/Elev= 30
  4577.0 1841.43  4591.0 1840.40  4616.6 1836.94  4623.0 1834.29  4648.6 1827.13
  4667.9 1823.21  4692.6 1821.37  4696.7 1821.74  4719.1 1820.37  4751.2 1819.97
  4782.1 1818.15  4872.9 1816.88  4975.5 1818.21  5002.0 1816.82  5002.3 1816.32
  5006.1 1816.32  5006.3 1816.82  5008.1 1817.35  5023.1 1817.97  5068.1 1818.32
  5101.8 1820.62  5113.1 1822.25  5154.3 1823.57  5190.7 1826.08  5321.9 1832.56
  5385.4 1838.61  5413.1 1840.56  5473.1 1847.00  5495.6 1847.43  5504.2 1848.52
#Mann=5,-1,0
  4577.0    0.07       0  4782.1   0.035       0  5002.0   0.035       0
  5006.3   0.035       0  5190.7    0.07       0
Bank Sta=5002,5006.3
Exp/Cntr=0.3,0.1

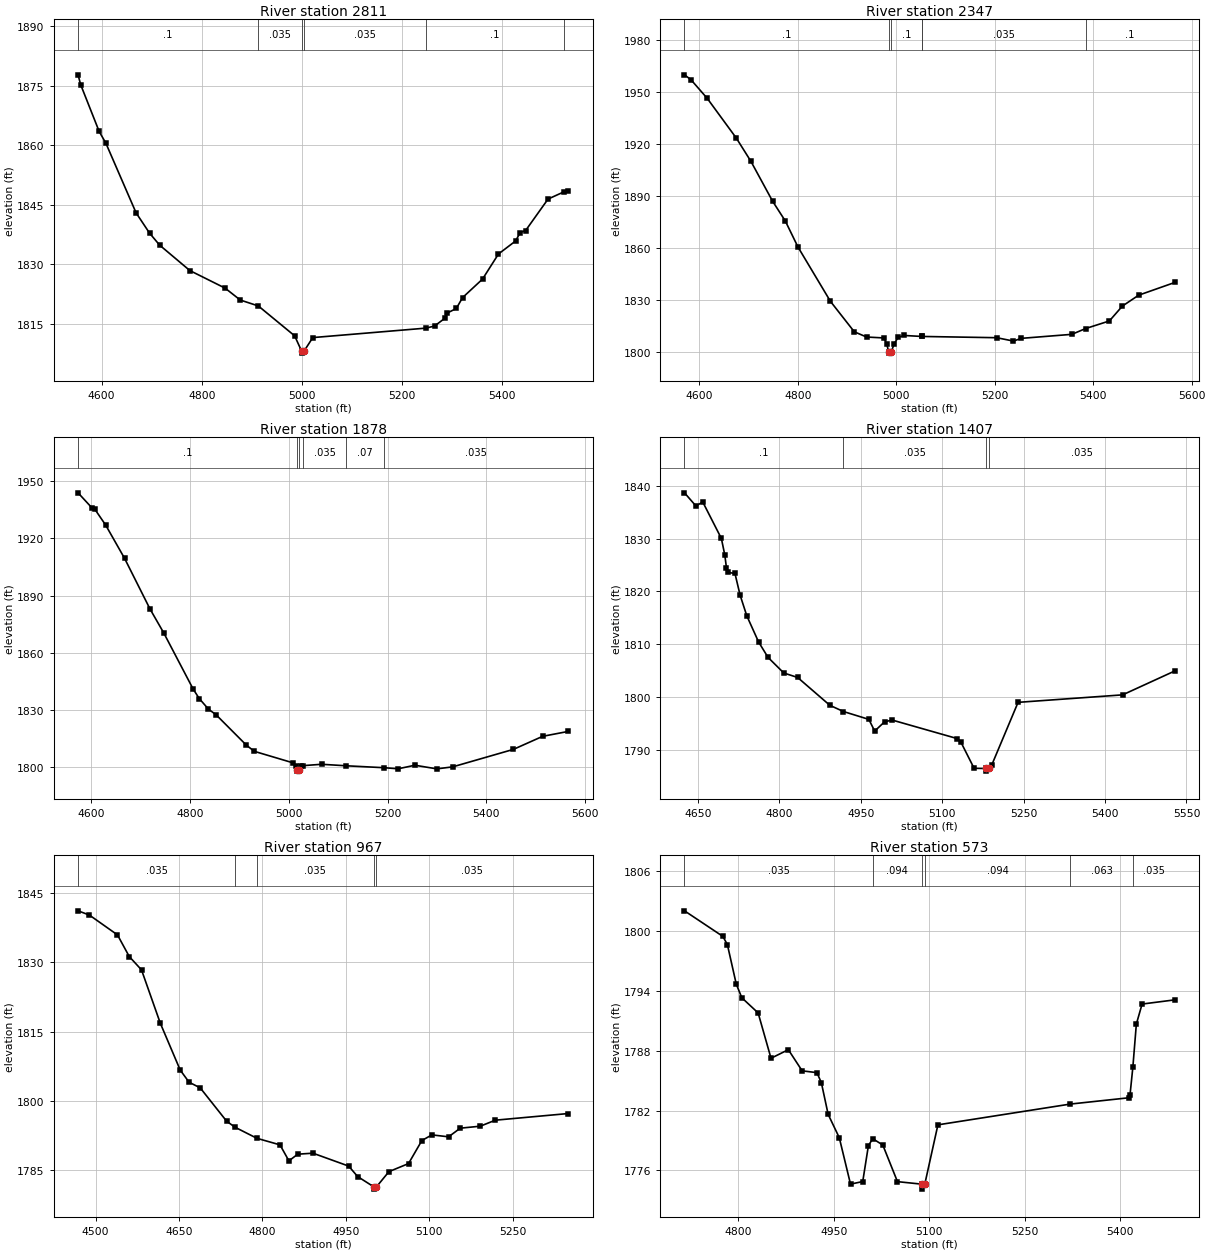
Type RM Length L Ch R = 1,2811,464,464,464
BEGIN DESCRIPTION:
Stream0465 5.0
END DESCRIPTION:
XS GIS Cut Line= 3
      1907224.99     13956375.02      1907025.00     13956775.00
      1906625.00     13957125.00
#Sta/Elev= 30
  4553.0 1877.71  4558.2 1875.24  4595.1 1863.47  4608.5 1860.52  4668.9 1842.97
  4695.7 1837.89  4715.8 1834.87  4776.2 1828.46  4846.6 1824.04  4876.8 1821.05
  4912.9 1819.56  4985.4 1812.04  4999.3 1808.19  4999.6 1807.69  5004.1 1808.19
  5021.6 1811.60  5247.4 1813.98  5264.7 1814.51  5285.3 1816.47  5289.8 1817.77
  5308.1 1818.92  5320.6 1821.66  5360.4 1826.31  5392.3 1832.64  5426.5 1835.91
  5435.6 1838.03  5446.5 1838.54  5491.2 1846.45  5524.0 1848.33  5531.7 1848.58
#Mann=6,-1,0
  4553.0     0.1       0  4912.9   0.035       0  4999.3   0.035       0
  5004.1   0.035       0  5247.4     0.1       0  5524.0    0.07       0
Bank Sta=4999.3,5004.1
Exp/Cntr=0.3,0.1

Type RM Length L Ch R = 1,2347,469,469,469
BEGIN DESCRIPTION:
Stream0465 4.0
END DESCRIPTION:
XS GIS Cut Line= 3
      1907025.01     13956074.98      1906775.00     13956425.00
      1906375.02     13956824.98
#Sta/Elev= 30
  4569.9 1959.96  4583.0 1957.16  4616.2 1946.35  4675.2 1923.46  4704.7 1910.14
  4748.9 1887.07  4774.7 1875.69  4800.5 1860.63  4866.3 1829.38  4914.8 1811.82
  4939.8 1808.80  4974.7 1808.28  4980.6 1805.04  4984.7 1800.02  4985.0 1799.52
  4989.5 1800.02  4995.9 1804.96  5003.8 1808.62  5016.5 1809.69  5051.4 1809.14
  5053.1 1809.13  5204.1 1808.41  5238.0 1806.47  5254.1 1808.04  5356.6 1810.35
  5384.6 1813.68  5432.9 1818.07  5459.3 1826.64  5492.3 1832.91  5565.7 1840.25
#Mann=6,-1,0
  4569.9     0.1       0  4984.7    0.05       0  4989.5     0.1       0
  5051.4    0.07       0  5053.1   0.035       0  5384.6     0.1       0
Bank Sta=4984.7,4989.5
Exp/Cntr=0.3,0.1

Type RM Length L Ch R = 1,1878,471,471,471
BEGIN DESCRIPTION:
Stream0465 3.0
END DESCRIPTION:
XS GIS Cut Line= 3
      1906875.03     13955924.99      1906475.00     13956075.00
      1906075.01     13956474.99
#Sta/Elev= 30
  4573.0 1943.90  4600.9 1936.08  4606.4 1935.52  4629.0 1926.95  4667.3 1909.49
  4718.6 1883.03  4746.7 1870.35  4806.0 1841.02  4818.4 1836.01  4837.1 1830.44
  4852.6 1827.47  4914.0 1811.52  4930.0 1808.31  5008.0 1802.30  5013.4 1800.69
  5016.2 1798.43  5016.5 1797.93  5021.0 1798.43  5024.9 1800.50  5029.0 1800.81
  5066.2 1801.52  5115.5 1800.74  5193.6 1799.71  5221.2 1799.16  5255.2 1801.02
  5299.6 1799.12  5331.6 1800.16  5454.6 1809.33  5514.0 1816.19  5565.9 1818.76
#Mann=6,-1,0
  4573.0     0.1       0  5016.2    0.05       0  5021.0     0.1       0
  5029.0   0.035       0  5115.5    0.07       0  5193.6   0.035       0
Bank Sta=5016.2,5021
Exp/Cntr=0.3,0.1

Type RM Length L Ch R = 1,1407,440,440,440
BEGIN DESCRIPTION:
Stream0465 2.0
END DESCRIPTION:
XS GIS Cut Line= 3
      1906525.04     13955624.99      1906175.00     13955725.00
      1905895.96     13956185.74
#Sta/Elev= 30
  4625.7 1838.72  4646.8 1836.22  4659.3 1836.99  4693.6 1830.06  4699.9 1826.93
  4703.0 1824.46  4706.1 1823.61  4718.6 1823.43  4728.0 1819.34  4740.4 1815.39
  4762.1 1810.43  4779.5 1807.50  4808.5 1804.54  4834.0 1803.69  4893.3 1798.41
  4918.3 1797.23  4965.1 1795.74  4975.9 1793.52  4994.0 1795.27  5008.1 1795.61
  5127.3 1792.11  5134.6 1791.43  5158.9 1786.46  5181.0 1786.42  5181.4 1785.92
  5185.8 1786.42  5191.4 1787.07  5239.9 1798.97  5432.4 1800.39  5528.4 1804.92
#Mann=4,-1,0
  4625.7     0.1       0  4918.3   0.035       0  5181.0   0.035       0
  5185.8   0.035       0
Bank Sta=5181,5185.8
Exp/Cntr=0.3,0.1

Type RM Length L Ch R = 1,967,394,394,394
BEGIN DESCRIPTION:
Stream0465 1.0
END DESCRIPTION:
XS GIS Cut Line= 3
      1906325.00     13955175.00      1905925.00     13955525.00
      1905925.00     13955874.99
#Sta/Elev= 30
  4468.5 1841.13  4488.8 1840.22  4539.4 1835.92  4560.6 1831.23  4582.6 1828.35
  4616.4 1816.80  4652.2 1806.66  4668.2 1804.03  4688.1 1802.82  4735.6 1795.61
  4750.7 1794.30  4790.1 1791.90  4831.6 1790.48  4847.6 1787.02  4863.5 1788.46
  4890.8 1788.68  4955.2 1785.88  4971.1 1783.63  5000.2 1781.40  5000.6 1780.90
  5005.1 1781.40  5027.4 1784.68  5062.7 1786.43  5086.7 1791.42  5104.7 1792.64
  5134.7 1792.22  5155.7 1794.09  5191.7 1794.52  5218.7 1795.82  5350.0 1797.26
#Mann=5,-1,0
  4468.5   0.035       0  4750.7     0.1       0  4790.1   0.035       0
  5000.2   0.035       0  5005.1   0.035       0
Bank Sta=5000.2,5005.1
Exp/Cntr=0.3,0.1

Type RM Length L Ch R = 1,573,0,0,0
BEGIN DESCRIPTION:
Stream0465 0.0
END DESCRIPTION:
XS GIS Cut Line= 3
      1906016.12     13955038.38      1905661.27     13955255.14
      1905662.98     13955608.91
#Sta/Elev= 30
  4715.9 1802.01  4776.1 1799.45  4783.2 1798.63  4797.2 1794.66  4805.9 1793.30
  4831.5 1791.78  4851.7 1787.24  4878.9 1788.10  4900.6 1785.98  4923.8 1785.80
  4930.8 1784.78  4941.4 1781.62  4958.9 1779.28  4976.5 1774.63  4995.7 1774.89
  5004.6 1778.49  5011.4 1779.18  5027.2 1778.55  5050.2 1774.88  5088.0 1774.63
  5088.4 1774.13  5093.1 1774.63  5113.7 1780.57  5321.4 1782.65  5413.2 1783.28
  5415.3 1783.59  5419.7 1786.33  5425.2 1790.66  5434.2 1792.67  5485.5 1793.09
#Mann=6,-1,0
  4715.9   0.035       0  5011.4   0.094       0  5088.0   0.035       0
  5093.1   0.094       0  5321.4   0.063       0  5419.7   0.035       0
Bank Sta=5088,5093.1
Exp/Cntr=0.3,0.1

Chan Stop Cuts=-1