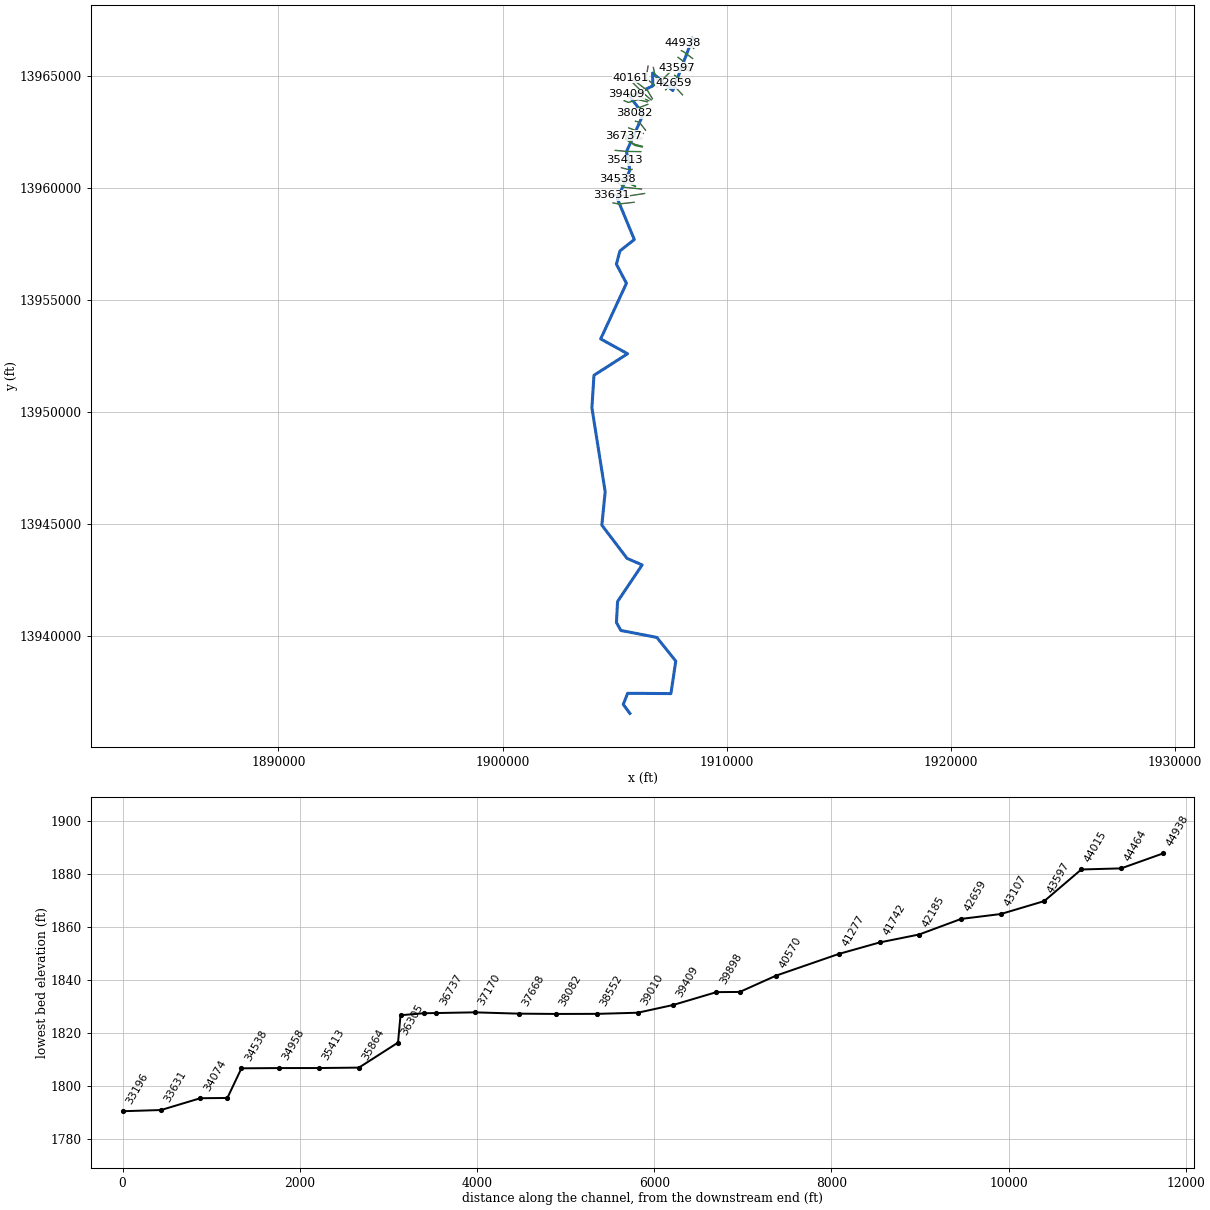
--- Goat Creek.prj (project) ---

Proj Title=Goat Creek Base Level Engineering
Current Plan=p01
Default Exp/Contr=0.3,0.1
English Units
Geom File=g01
Flow File=f01
Plan File=p01
Y Axis Title=Elevation
X Axis Title(PF)=Main Channel Distance
X Axis Title(XS)=Station
BEGIN DESCRIPTION:
Goat Creek
END DESCRIPTION:
DSS Export Rating Curves= 0
DSS Export Rating Curve Sorted= 0
DSS Export Volume Flow Curves= 0
DXF OffsetX= 0
DXF OffsetY= 0
DXF ScaleX= 1
DXF ScaleY= 10

--- Goat Creek.p01 (plan) ---

Plan Title=Multiple Run
Short Identifier=Multiple
Geom File=g01
Flow File=f01
Subcritical Flow
K Sum by GR= 0
Std Step Tol= 0.01
Critical Tol= 0.01
Num of Std Step Trials= 20
Max Error Tol= 0.3
Flow Tol Ratio= 0.001
Split Flow NTrial= 30
Split Flow Tol= 0.02
Split Flow Ratio= 0.02
Log Output Level= 0
Friction Slope Method= 1
Unsteady Friction Slope Method= 2
Unsteady Bridges Friction Slope Method= 1
Parabolic Critical Depth
Global Vel Dist=  1 , 1 , 1
Global Log Level= 0
CheckData=True
Encroach Param= -1, 0, 0, 0
BEGIN DESCRIPTION:
Multiple Run
END DESCRIPTION:

--- Goat Creek.f01 (steady flow) ---

Flow Title=Multiple
Program Version=4.10
Number of Profiles= 7
Profile Names=10-year,25-year,50-year,1pct_min,100-year,1pct_plu,500-year
River Rch & RM=Goat Creek,Reach-1         ,44938
    2218    3936    5631    3885    7752   15466   14524
River Rch & RM=Goat Creek,Reach-1         ,40161
    3929    7131   10357    7235   14437   28805   27757
River Rch & RM=Goat Creek,Reach-1         ,30431
    6547   12136   17878   12653   25245   50371   49810
River Rch & RM=Goat Creek,Reach-1         ,27672
    7397   13746   20284   14373   28677   57219   56719
River Rch & RM=Goat Creek,Reach-1         ,22111
    7449   13844   20428   14475   28882   57627   57122
River Rch & RM=Goat Creek,Reach-1         ,21902
    7431   13776   20294   14353   28638   57140   56429
River Rch & RM=Goat Creek,Reach-1         ,17478
    8732   16222   23939   16956   33831   67502   66820
River Rch & RM=Goat Creek,Reach-1         ,15952
    9207   17116   25269   17903   35721   71272   70584
River Rch & RM=Goat Creek,Reach-1         ,13116
    9390   17453   25763   18248   36410   72648   71915
River Rch & RM=Goat Creek,Reach-1         ,9993
    9400   17431   25688   18162   36239   72306   71317
Boundary for River Rch & Prof#=Goat Creek,Reach-1         , 1
Up Type= 0
Dn Type= 3
Dn Slope=0.006
Boundary for River Rch & Prof#=Goat Creek,Reach-1         , 2
Up Type= 0
Dn Type= 3
Dn Slope=0.006
Boundary for River Rch & Prof#=Goat Creek,Reach-1         , 3
Up Type= 0
Dn Type= 3
Dn Slope=0.006
Boundary for River Rch & Prof#=Goat Creek,Reach-1         , 4
Up Type= 0
Dn Type= 3
Dn Slope=0.006
Boundary for River Rch & Prof#=Goat Creek,Reach-1         , 5
Up Type= 0
Dn Type= 3
Dn Slope=0.006
Boundary for River Rch & Prof#=Goat Creek,Reach-1         , 6
Up Type= 0
Dn Type= 3
Dn Slope=0.006
Boundary for River Rch & Prof#=Goat Creek,Reach-1         , 7
Up Type= 0
Dn Type= 3
Dn Slope=0.006
DSS Import GetInterval= 0
DSS Import GetPeak= 0
DSS Import FillOption= 0

--- Goat Creek.g01 (geometry) ---

Geom Title=Existing Conditions
Program Version=4.10

River Reach=Goat Creek      ,Reach-1
Reach XY= 30
        1908475.       13966675.      1907591.67     13964341.21
      1906690.07     13965124.82      1906702.23     13964551.43
      1905677.04     13964069.15      1906274.47     13963288.87
      1905527.18     13961619.55      1905674.19     13960785.71
      1905124.77     13959499.93      1905874.52     13957688.73
      1905232.83      13957178.4      1905075.54     13956585.64
      1905523.89     13955735.55       1904374.5     13953249.97
      1905574.41     13952586.83        1904075.       13951625.
      1903982.79      13950175.1        1904575.       13946425.
      1904426.84     13944931.12      1905551.42     13943447.84
      1906224.96     13943154.97      1905128.55     13941523.53
      1905077.26     13940580.94      1905276.45     13940228.53
      1906881.34     13939916.98      1907724.48     13938859.78
      1907508.37     13937408.29      1905576.46     13937421.47
      1905382.32      13936924.9        1905675.       13936525.

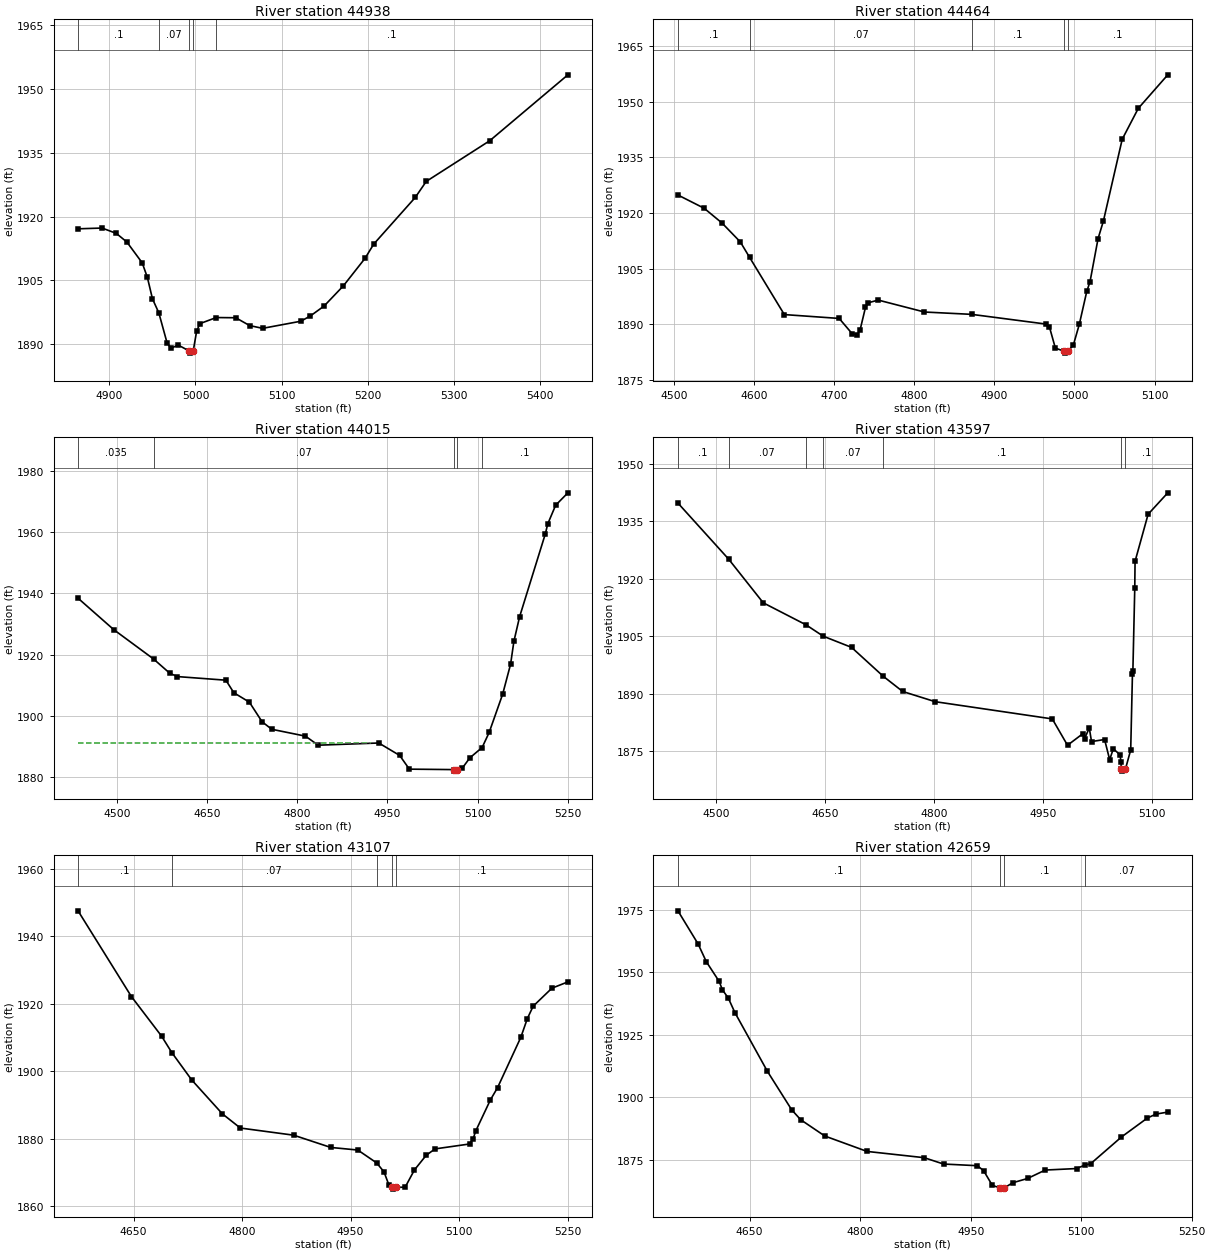
Type RM Length L Ch R = 1 ,44938   ,474,474,474
BEGIN DESCRIPTION:
Goat Creek 82.0
END DESCRIPTION:
XS GIS Cut Line= 3
      1908524.97     13966225.03        1908425.       13966325.
      1908024.98     13966475.01
#Sta/Elev= 30
  4863.7 1917.13  4891.6 1917.31  4908.1 1916.06  4920.4 1914.02  4938.2 1909.12
  4944.2 1905.69  4950.1 1900.66  4957.5 1897.35    4967 1890.34  4971.7 1889.02
  4979.8 1889.81  4992.8 1888.39  4993.1 1887.89  4997.4 1888.39  5001.4 1893.09
  5005.2 1894.83  5024.1 1896.26  5046.8 1896.21  5062.9 1894.37    5078 1893.72
  5122.2 1895.39  5133.3 1896.62  5149.4 1898.98  5171.8 1903.74  5196.8 1910.18
    5207 1913.55  5255.1  1924.5  5267.9 1928.28  5341.6 1937.85  5432.3 1953.35
#Mann= 5 ,-1 , 0
  4863.7      .1       0  4957.5     .07       0  4992.8     .05       0
  4997.4     .07       0  5024.1      .1       0
Bank Sta=4992.8,4997.4
XS Rating Curve= 0 ,0
Exp/Cntr=0.3,0.1

Type RM Length L Ch R = 1 ,44464   ,449,449,449
BEGIN DESCRIPTION:
Goat Creek 81.0
END DESCRIPTION:
XS GIS Cut Line= 3
      1908475.02     13965774.99        1908075.       13966075.
      1907975.02     13966124.99
#Sta/Elev= 30
  4504.7 1924.85  4537.5 1921.27  4559.8 1917.29  4582.6 1912.21  4594.1 1908.08
  4637.6 1892.62  4706.1 1891.58  4722.6 1887.39  4728.6  1887.2  4732.3 1888.56
  4738.9 1894.53  4742.6 1895.81  4754.8 1896.53  4812.6 1893.31  4871.5 1892.68
  4964.8 1890.05  4968.6 1889.36  4976.1 1883.58  4987.3 1882.73  4987.6 1882.23
  4991.9 1882.73  4998.6 1884.43    5006 1889.99  5015.3 1898.85  5019.4  1901.5
  5029.4 1913.06  5036.1 1917.84  5059.6 1939.88  5079.7 1948.21  5116.5 1957.24
#Mann= 5 ,-1 , 0
  4504.7      .1       0  4594.1     .07       0  4871.5      .1       0
  4987.3     .05       0  4991.9      .1       0
Bank Sta=4987.3,4991.9
XS Rating Curve= 0 ,0
Exp/Cntr=0.3,0.1

Type RM Length L Ch R = 1 ,44015   ,418,418,418
BEGIN DESCRIPTION:
Goat Creek 80.0
END DESCRIPTION:
XS GIS Cut Line= 3
      1908425.01     13965274.99        1908025.       13965675.
        1907825.       13965825.
#Sta/Elev= 30
  4434.8 1938.43  4494.4 1928.12  4560.5 1918.54  4587.7 1913.84  4600.4 1912.77
    4681 1911.59  4694.2 1907.49  4720.1  1904.4  4741.3 1897.98  4757.4 1895.52
  4813.5 1893.27  4834.7 1890.31  4935.6 1891.03  4970.4 1886.96  4986.5 1882.47
  5060.2 1882.32  5060.7 1881.82    5066 1882.32  5074.4 1882.73  5087.3 1886.18
  5107.7 1889.55  5119.4 1894.48  5141.9 1907.02  5155.1 1916.84  5160.6 1924.32
  5170.1 1932.36  5213.1 1959.59  5216.9 1962.72  5230.1 1968.86  5250.5 1972.93
#Mann= 5 ,-1 , 0
  4434.8    .035       0  4560.5     .07       0  5060.2     .05       0
    5066     .07       0  5107.7      .1       0
#XS Ineff= 2 , 0
         4923.26 1891.07
Permanent Ineff=
       F       F
Bank Sta=5060.2,5066
XS Rating Curve= 0 ,0
Exp/Cntr=0.3,0.1

Type RM Length L Ch R = 1 ,43597   ,490,490,490
BEGIN DESCRIPTION:
Goat Creek 79.0
END DESCRIPTION:
XS GIS Cut Line= 3
      1908397.06      13965191.4      1907940.34     13965361.98
      1907752.86     13965370.31
#Sta/Elev= 30
    4447 1939.75  4516.8 1925.16  4564.6 1913.75  4623.4 1908.03  4647.3 1905.05
  4686.3 1902.14  4729.9 1894.62  4756.8 1890.64  4801.6 1887.98    4963 1883.49
    4984 1876.62    5005 1879.62  5007.5 1878.35    5014 1881.12  5017.1 1877.59
  5035.1 1878.12  5042.1 1872.87  5047.1 1875.69  5056.1  1874.2  5057.8 1872.38
    5058 1870.38  5058.5 1869.88  5063.8 1870.38  5071.1 1875.41  5073.5 1895.14
  5074.1 1896.06  5076.7 1917.59  5077.1 1924.56  5095.1 1936.84  5122.2 1942.42
#Mann= 7 ,-1 , 0
    4447      .1       0  4516.8     .07       0  4623.4    .035       0
  4647.3     .07       0  4729.9      .1       0    5058     .05       0
  5063.8      .1       0
Bank Sta=5058,5063.8
XS Rating Curve= 0 ,0
Exp/Cntr=0.3,0.1

Type RM Length L Ch R = 1 ,43107   ,448,448,448
BEGIN DESCRIPTION:
Goat Creek 78.0
END DESCRIPTION:
XS GIS Cut Line= 3
      1908275.01       13964725.        1907875.       13964875.
      1907675.01       13965025.
#Sta/Elev= 30
  4573.2 1947.58    4647 1922.13  4688.7 1910.39  4702.8 1905.53  4730.3 1897.41
  4772.7 1887.34  4797.6 1883.12  4871.3    1881  4922.6 1877.36    4960 1876.59
  4986.1 1872.76  4996.2  1870.1    5003  1866.2  5007.6 1865.49  5008.1 1864.99
  5013.4 1865.49  5025.5 1865.59  5038.3  1870.7  5054.6 1875.05  5066.8 1876.93
  5114.6 1878.39  5119.3 1879.86    5123 1882.24  5143.3 1891.48  5153.2 1895.11
  5185.3 1910.02  5194.3 1915.57  5202.4 1919.28  5228.3 1924.62  5250.4 1926.49
#Mann= 5 ,-1 , 0
  4573.2      .1       0  4702.8     .07       0  4986.1      .1       0
  5007.6     .05       0  5013.4      .1       0
Bank Sta=5007.6,5013.4
XS Rating Curve= 0 ,0
Exp/Cntr=0.3,0.1

Type RM Length L Ch R = 1 ,42659   ,474,474,474
BEGIN DESCRIPTION:
Goat Creek 77.0
END DESCRIPTION:
XS GIS Cut Line= 3
      1908025.09     13964151.67        1907725.       13964475.
      1907625.02     13964674.97
#Sta/Elev= 30
  4552.8 1974.59  4580.2 1961.31  4591.3 1954.23  4608.8  1946.3  4613.1 1942.99
  4621.1 1939.67  4630.1 1933.84  4674.3 1910.27  4707.1 1894.94  4719.3 1890.95
  4752.1 1884.41  4809.4 1878.24    4887 1875.73  4913.2 1873.19  4959.1 1872.52
  4967.6 1870.53  4979.4 1864.65  4989.7 1863.64  4990.2 1863.14  4995.6 1863.64
  5007.1 1865.69  5027.2  1867.4  5051.2 1870.78  5093.7 1871.38  5105.3  1872.8
  5112.7 1873.27  5154.6 1884.01  5189.8 1891.61  5201.6  1893.2  5217.5 1893.99
#Mann= 4 ,-1 , 0
  4552.8      .1       0  4989.7     .05       0  4995.6      .1       0
  5105.3     .07       0
Bank Sta=4989.7,4995.6
XS Rating Curve= 0 ,0
Exp/Cntr=0.3,0.1

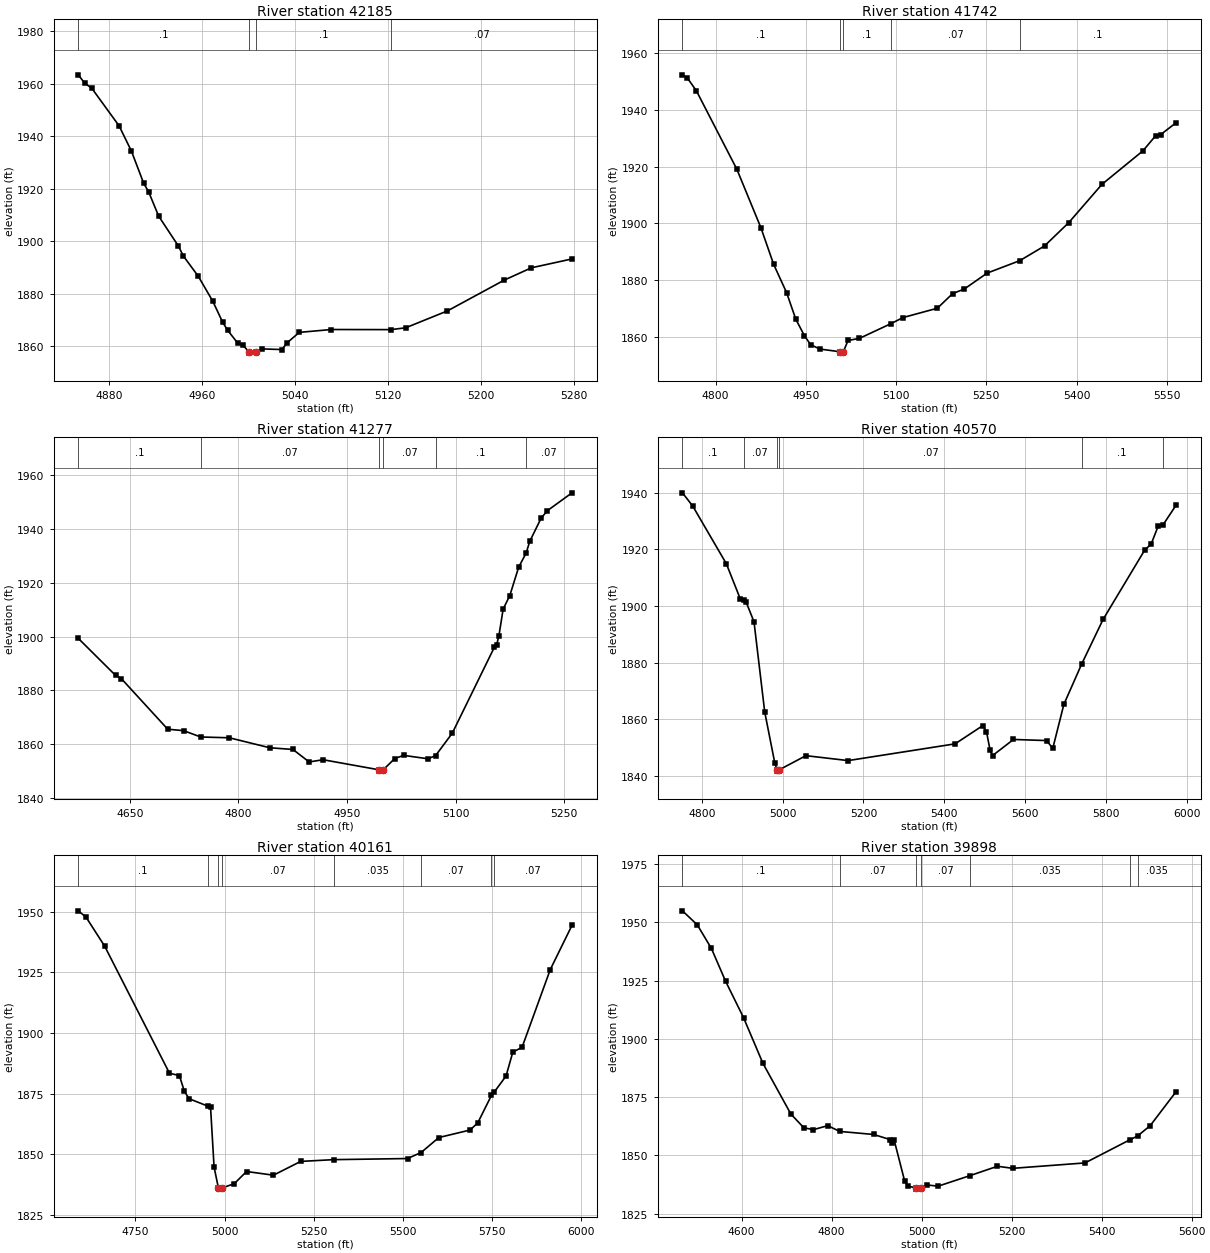
Type RM Length L Ch R = 1 ,42185   ,443,443,443
BEGIN DESCRIPTION:
Goat Creek 76.0
END DESCRIPTION:
XS GIS Cut Line= 3
      1907275.01     13964375.01        1907375.       13964475.
      1907574.97     13964674.97
#Sta/Elev= 30
  4853.8 1963.46  4859.3 1960.33  4865.5  1958.3  4888.9 1943.99  4899.5 1934.35
  4910.1 1921.99  4914.2  1918.9  4922.9 1909.53  4939.9 1898.09    4944 1894.39
  4956.9  1886.6  4969.4 1877.06  4977.9 1869.01  4982.2 1865.95  4990.7 1861.14
  4995.1 1860.41  5000.4 1857.75  5000.9 1857.25  5006.3 1857.75    5012 1858.86
  5028.8 1858.61  5033.1 1861.13  5043.7 1865.17  5071.3 1866.26  5122.5 1866.22
  5135.1 1866.92    5171 1873.37  5219.9 1885.14  5243.1 1889.81    5278  1893.2
#Mann= 4 ,-1 , 0
  4853.8      .1       0  5000.4     .05       0  5006.3      .1       0
  5122.5     .07       0
Bank Sta=5000.4,5006.3
XS Rating Curve= 0 ,0
Exp/Cntr=0.3,0.1

Type RM Length L Ch R = 1 ,41742   ,465,465,465
BEGIN DESCRIPTION:
Goat Creek 75.0
END DESCRIPTION:
XS GIS Cut Line= 3
        1907075.     13964574.98        1907125.       13964825.
      1907525.03     13965225.03
#Sta/Elev= 30
    4745 1952.32  4752.9 1951.29  4768.2 1946.69  4835.5 1919.03  4875.3 1898.52
  4896.7 1885.51  4918.1  1875.6  4933.4 1866.22  4947.8  1860.4  4957.9 1857.28
  4973.2 1855.71  5006.5 1854.77    5007 1854.27  5012.5 1854.77  5020.2 1858.72
  5039.3 1859.48  5091.6 1864.66  5111.6  1866.8  5168.7 1870.09  5194.2 1875.26
  5213.4 1876.84  5251.4 1882.46  5305.8 1886.86  5346.9 1892.04  5387.2 1900.27
  5442.4 1913.76  5510.4 1925.54  5531.3 1930.81  5540.1 1931.29  5565.7 1935.48
#Mann= 5 ,-1 , 0
    4745      .1       0  5006.5     .05       0  5012.5      .1       0
  5091.6     .07       0  5305.8      .1       0
Bank Sta=5006.5,5012.5
XS Rating Curve= 0 ,0
Exp/Cntr=0.3,0.1

Type RM Length L Ch R = 1 ,41277   ,707,707,707
BEGIN DESCRIPTION:
Goat Creek 74.0
END DESCRIPTION:
XS GIS Cut Line= 3
        1906925.     13964725.01        1906775.       13965125.
      1906725.01     13965374.96
#Sta/Elev= 30
  4578.7 1899.33  4630.2 1885.55  4638.2 1884.34  4702.3  1865.5  4724.2 1864.96
  4747.9  1862.6  4787.5  1862.3  4843.3 1858.59  4875.3 1857.95  4897.7 1853.31
    4917 1854.13  4994.1 1850.39  4994.6 1849.89  5000.1 1850.39  5015.8 1854.54
  5028.1 1855.76  5061.7 1854.49  5072.3 1855.65  5095.4 1864.01  5153.5 1895.99
  5156.6 1896.85  5159.7 1900.06  5165.7 1910.23  5174.9 1915.26  5187.1  1925.8
  5197.5 1931.11  5202.4  1935.4  5218.2  1944.1  5226.9 1946.88  5260.8  1953.5
#Mann= 6 ,-1 , 0
  4578.7      .1       0  4747.9     .07       0  4994.1     .05       0
  5000.1     .07       0  5072.3      .1       0  5197.5     .07       0
Bank Sta=4994.1,5000.1
XS Rating Curve= 0 ,0
Exp/Cntr=0.3,0.1

Type RM Length L Ch R = 1 ,40570   ,409,409,409
BEGIN DESCRIPTION:
Goat Creek 73.0
END DESCRIPTION:
XS GIS Cut Line= 4
      1906920.76     13964480.18      1906729.28     13964628.79
      1906398.56      13964878.6      1906489.02     13965436.17
#Sta/Elev= 30
  4752.2 1939.95  4777.6  1935.3  4860.8 1914.93    4895 1902.62  4903.4 1902.02
  4910.2 1901.26  4929.3 1894.41  4955.8 1862.59  4980.6 1844.64  4986.1  1842.2
  4986.6  1841.7  4992.2  1842.2  5057.7 1847.16  5162.1 1845.42  5426.9 1851.33
  5495.3 1857.77  5504.4 1855.66  5513.5 1849.04  5519.6 1847.19  5571.3 1852.88
  5653.3 1852.49  5668.5 1849.71  5695.9 1865.24  5740.2 1879.57  5793.1 1895.29
  5896.5 1919.86  5911.7 1921.78    5929  1928.1  5940.4 1928.45  5973.9 1935.65
#Mann= 6 ,-1 , 0
  4752.2      .1       0  4903.4     .07       0  4986.1     .05       0
  4992.2     .07       0  5740.2      .1       0  5940.4     .07       0
#XS Ineff= 2 , 0
                         5495.35         1857.43
Permanent Ineff=
       F       F
Bank Sta=4986.1,4992.2
XS Rating Curve= 0 ,0
Exp/Cntr=0.3,0.1

Type RM Length L Ch R = 1 ,40161   ,263,263,263
BEGIN DESCRIPTION:
Goat Creek 72.0
END DESCRIPTION:
XS GIS Cut Line= 3
      1906682.66     13963976.09      1906464.08     13964341.35
      1905700.33     13964922.86
#Sta/Elev= 30
  4589.4 1950.36  4611.1  1947.8  4663.6 1935.78  4845.4 1883.38  4873.3 1882.37
  4887.3 1875.89  4900.5 1872.84  4953.9 1869.75  4960.7 1869.41  4970.6 1844.68
  4982.7 1836.05  4983.2 1835.55  4993.6 1836.05  5027.3 1837.81  5061.8 1842.82
  5137.2  1841.3  5213.8 1846.99  5306.5 1847.71  5513.5 1848.17  5551.6 1850.66
  5601.3 1856.83  5689.1 1859.94  5710.7 1862.92  5748.9  1874.2  5756.8 1875.61
  5789.9 1882.21    5809 1892.11  5834.8 1894.03    5914 1926.12    5975 1944.38
#Mann= 8 ,-1 , 0
  4589.4      .1       0  4953.9     .07       0  4982.7     .05       0
  4993.6     .07       0  5306.5    .035       0  5551.6     .07       0
  5748.9    .035       0  5756.8     .07       0
Bank Sta=4982.7,4993.6
XS Rating Curve= 0 ,0
Exp/Cntr=0.3,0.1

Type RM Length L Ch R = 1 ,39898   ,489,489,489
BEGIN DESCRIPTION:
Goat Creek 71.0
END DESCRIPTION:
XS GIS Cut Line= 3
      1906625.02     13963924.98        1906225.       13964275.
      1905825.01     13964674.99
#Sta/Elev= 30
  4468.5 1954.98  4501.5 1948.96  4532.9 1938.82  4564.3 1924.78  4604.2 1909.15
  4647.3 1889.52  4709.4 1867.74  4738.4  1861.8  4759.7 1861.02  4791.5 1862.74
  4817.9 1860.26  4893.3 1858.95  4929.8 1856.77  4934.3 1855.23    4939 1856.53
  4962.4 1838.86  4970.8 1836.72  4988.1 1835.98  4988.6 1835.48    4999 1835.98
    5011 1837.29  5036.7 1836.75  5107.3 1841.27  5168.5  1845.3  5202.4 1844.41
  5363.1 1846.73  5463.2 1856.71  5479.8 1858.29  5507.9 1862.73  5565.7 1877.39
#Mann= 7 ,-1 , 0
  4468.5      .1       0  4817.9     .07       0  4988.1     .05       0
    4999     .07       0  5107.3    .035       0  5463.2     .07       0
  5479.8    .035       0
Bank Sta=4988.1,4999
XS Rating Curve= 0 ,0
Exp/Cntr=0.3,0.1

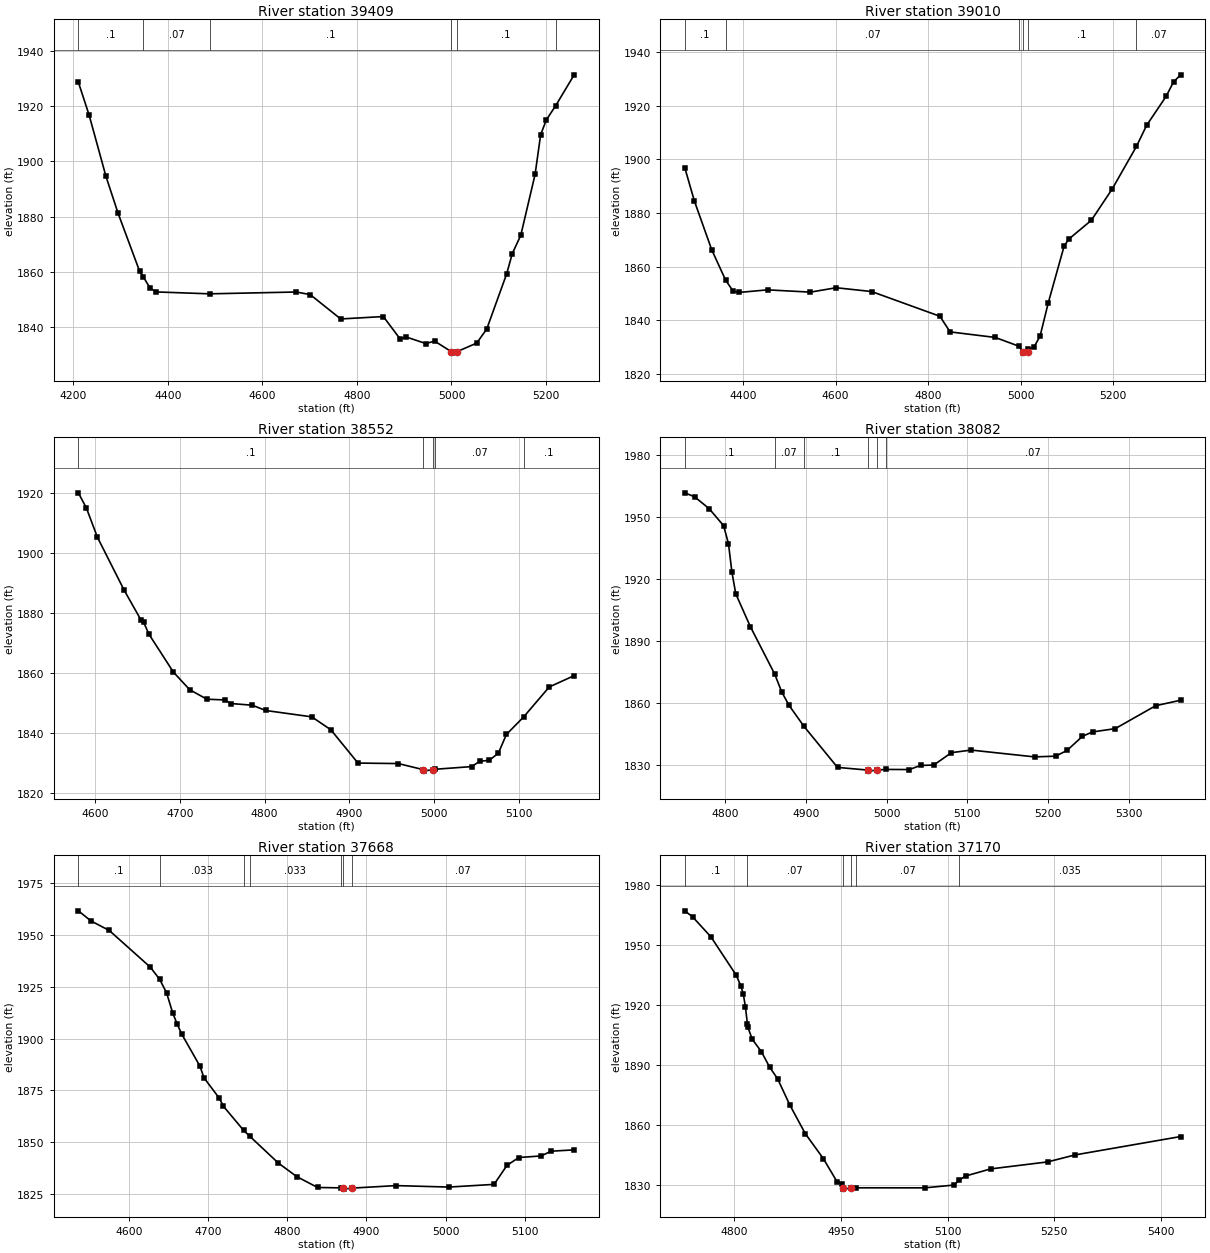
Type RM Length L Ch R = 1 ,39409   ,399,399,399
BEGIN DESCRIPTION:
Goat Creek 70.0
END DESCRIPTION:
XS GIS Cut Line= 4
       1906520.3     13963889.34      1905860.45     13964148.41
      1905777.98       13964175.      1905525.02       13964175.
#Sta/Elev= 30
  4210.9 1928.68  4233.9 1916.62  4269.3 1894.57  4294.8 1881.29  4340.3 1860.33
  4347.8 1858.32  4362.8 1854.11  4375.7 1852.76  4488.6 1852.07  4671.7 1852.73
  4701.2  1851.8  4765.7 1842.98  4855.9 1843.85  4891.4 1835.74  4904.3 1836.45
  4945.6  1834.1  4964.5 1834.95    5000 1831.12  5000.5 1830.62  5011.2 1831.12
  5053.3 1834.25  5074.5 1839.32  5116.8 1859.36  5128.5 1866.61  5146.5 1873.24
  5176.8 1895.28  5188.5  1909.6  5200.5 1914.97  5220.1 1920.07  5259.4 1931.29
#Mann= 6 ,-1 , 0
  4210.9      .1       0  4347.8     .07       0  4488.6      .1       0
    5000     .05       0  5011.2      .1       0  5220.1     .07       0
Bank Sta=5000,5011.2
XS Rating Curve= 0 ,0
Exp/Cntr=0.3,0.1

Type RM Length L Ch R = 1 ,39010   ,458,458,458
BEGIN DESCRIPTION:
Goat Creek 69.0
END DESCRIPTION:
XS GIS Cut Line= 5
      1906450.38     13963836.96      1906044.06       13963939.
      1905733.81     13963845.59      1905607.69     13963814.59
      1905422.65      13963889.1
#Sta/Elev= 30
  4273.9 1896.84  4294.7  1884.4  4332.1 1866.26  4362.2 1854.91  4378.5 1850.81
  4390.9 1850.33  4452.8  1851.3  4545.6 1850.45  4601.2 1852.09  4677.9 1850.67
  4825.6 1841.45  4847.6 1835.62  4945.2 1833.55  4997.3 1830.23  5004.9  1828.2
  5005.4  1827.7  5016.1  1828.2  5016.8 1829.09  5029.1 1829.95  5042.3  1834.1
    5060  1846.5  5094.3 1867.64  5104.3 1870.22    5153 1877.22  5198.2 1888.92
  5250.6 1904.78  5272.6 1912.64  5314.7 1923.43  5330.8 1928.83  5346.2  1931.5
#Mann= 6 ,-1 , 0
  4273.9      .1       0  4362.2     .07       0  4997.3      .1       0
  5004.9     .05       0  5016.1      .1       0  5250.6     .07       0
Bank Sta=5004.9,5016.1
XS Rating Curve= 0 ,0
Exp/Cntr=0.3,0.1

Type RM Length L Ch R = 1 ,38552   ,470,470,470
BEGIN DESCRIPTION:
Goat Creek 68.0
END DESCRIPTION:
XS GIS Cut Line= 3
      1906474.99       13963725.        1906075.       13963575.
      1905925.01       13963525.
#Sta/Elev= 30
  4580.1 1920.11  4589.7 1914.99  4602.6  1905.3    4634 1887.73  4653.9 1877.76
  4657.1 1876.97  4663.5 1872.93  4692.3 1860.31  4711.6 1854.42  4731.8 1851.27
  4753.2 1851.01  4759.8 1849.83  4785.4 1849.26  4801.3  1847.5  4855.7 1845.37
  4878.2 1841.06  4910.2 1829.96  4957.9 1829.79  4987.2 1827.77  4987.7 1827.27
  4998.4 1827.77  5001.6  1827.9  5044.3 1828.78  5054.2 1830.58    5065 1830.85
  5075.9 1833.23  5085.4  1839.5  5105.9 1845.39    5136 1855.35  5165.4 1859.12
#Mann= 5 ,-1 , 0
  4580.1      .1       0  4987.2     .05       0  4998.4      .1       0
  5001.6     .07       0  5105.9      .1       0
Bank Sta=4987.2,4998.4
XS Rating Curve= 0 ,0
Exp/Cntr=0.3,0.1

Type RM Length L Ch R = 1 ,38082   ,414,414,414
BEGIN DESCRIPTION:
Goat Creek 67.0
END DESCRIPTION:
XS GIS Cut Line= 3
      1906474.97       13963225.        1906225.       13963225.
      1905874.98     13963325.01
#Sta/Elev= 30
    4750 1961.91  4762.1 1959.99  4780.1 1954.27  4798.1    1946  4804.1 1937.25
  4808.3 1923.68  4813.1 1913.05  4831.1 1897.21  4861.3 1874.22  4870.1 1865.49
  4879.1 1859.06  4897.5 1848.94  4939.1 1829.05  4976.7 1827.74  4977.2 1827.24
  4987.9 1827.74  4998.9 1828.06  5028.1    1828  5041.9 1829.99  5058.3 1830.18
  5080.2 1836.18  5104.6 1837.43  5183.1 1834.13  5209.3 1834.48  5223.3 1837.24
  5242.4 1844.09  5254.9 1846.21    5283  1847.8  5333.1  1858.9    5364 1861.54
#Mann= 6 ,-1 , 0
    4750      .1       0  4861.3     .07       0  4897.5      .1       0
  4976.7     .05       0  4987.9      .1       0  4998.9     .07       0
Bank Sta=4976.7,4987.9
XS Rating Curve= 0 ,0
Exp/Cntr=0.3,0.1

Type RM Length L Ch R = 1 ,37668   ,498,498,498
BEGIN DESCRIPTION:
Goat Creek 66.0
END DESCRIPTION:
XS GIS Cut Line= 3
      1906375.01     13962574.99      1906102.61     13962921.95
      1905924.98     13962975.01
#Sta/Elev= 30
  4535.9 1961.75  4552.1 1956.81    4575 1952.26  4626.8 1934.57  4638.8 1928.59
  4647.5 1922.03  4655.1 1912.48  4660.8 1907.06  4666.5 1902.24  4689.4 1886.85
  4694.8 1881.05  4714.2 1871.16  4719.1 1867.42  4744.8 1855.71  4752.2 1853.01
  4788.6 1839.95  4811.8 1833.43  4838.2 1828.14  4868.2 1827.96  4870.5 1827.85
    4871 1827.35  4882.1 1827.85  4937.3 1829.05  5004.2 1828.35  5061.2 1829.64
  5077.6 1838.88  5092.6 1842.62  5120.7 1843.38  5133.3 1845.67  5162.4 1846.31
#Mann= 7 ,-1 , 0
  4535.9      .1       0  4638.8    .033       0  4744.8      .1       0
  4752.2    .033       0  4868.2     .07       0  4870.5     .05       0
  4882.1     .07       0
Bank Sta=4870.5,4882.1
XS Rating Curve= 0 ,0
Exp/Cntr=0.3,0.1

Type RM Length L Ch R = 1 ,37170   ,433,433,433
BEGIN DESCRIPTION:
Goat Creek 65.0
END DESCRIPTION:
XS GIS Cut Line= 3
      1906274.99       13962425.        1906025.       13962525.
      1905625.04     13962674.98
#Sta/Elev= 30
    4731 1967.14  4741.9 1964.14  4767.7 1954.12  4803.3 1934.88  4809.7 1929.55
  4813.2 1925.44  4816.2 1918.96    4819 1910.28  4819.4    1909  4825.9 1902.75
  4838.6 1896.65  4850.1 1888.94  4861.4 1883.04  4878.4 1870.02  4900.2 1855.64
  4925.5 1843.16  4944.7 1831.63  4951.9 1830.49  4952.8 1828.34  4953.3 1827.84
  4964.4 1828.34  4971.5  1828.5  5067.9 1828.48  5109.3 1829.89  5115.7 1832.16
  5125.3  1834.4  5160.6 1837.96  5240.7 1841.47  5279.1 1844.96  5427.4 1854.16
#Mann= 6 ,-1 , 0
    4731      .1       0    4819     .07       0  4952.8     .05       0
  4964.4     .07       0  4971.5     .07       0  5115.7    .035       0
Bank Sta=4952.8,4964.4
XS Rating Curve= 0 ,0
Exp/Cntr=0.3,0.1

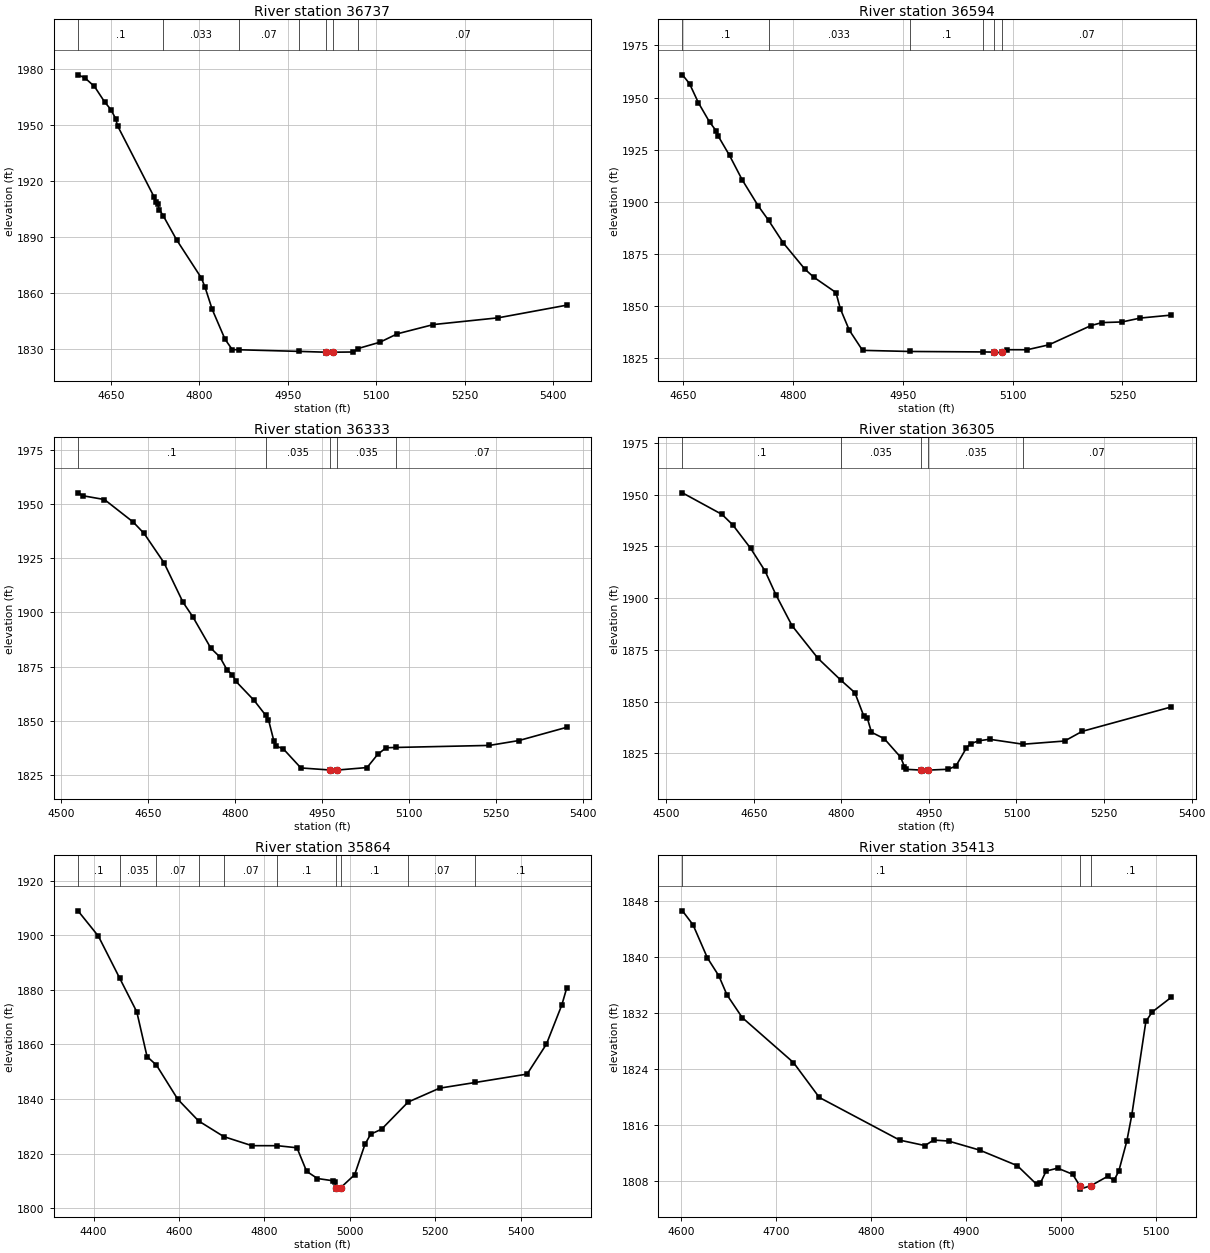
Type RM Length L Ch R = 1 ,36737   ,143,143,143
BEGIN DESCRIPTION:
Goat Creek 64.0
END DESCRIPTION:
XS GIS Cut Line= 3
      1906225.04     13962224.99        1905825.       13962325.
      1905407.68     13962320.25
#Sta/Elev= 30
  4593.8 1976.75  4605.3 1975.17  4621.8 1970.51  4639.3 1962.09  4649.8 1958.09
  4657.8 1953.17  4660.9 1949.48  4722.8 1911.41  4725.9 1908.72    4729 1907.41
  4732.1 1904.42  4738.7  1901.1  4761.1 1888.37  4803.2 1867.87  4809.4 1862.98
  4821.7 1850.97  4843.4 1835.03  4855.8 1829.42  4866.8 1829.39  4969.3 1828.51
  5014.4 1828.08  5014.9 1827.58  5026.2 1828.08  5061.3 1828.19  5069.2 1830.04
  5106.3 1833.43    5136 1837.95  5197.2  1842.9  5307.3 1846.52  5423.5 1853.29
#Mann= 7 ,-1 , 0
  4593.8      .1       0  4738.7    .033       0  4866.8     .07       0
  4969.3     .07       0  5014.4     .05       0  5026.2     .07       0
  5069.2     .07       0
Bank Sta=5014.4,5026.2
XS Rating Curve= 0 ,0
Exp/Cntr=0.3,0.1

Type RM Length L Ch R = 1 ,36594   ,261,261,261
BEGIN DESCRIPTION:
Mapping XS a883e0a5
END DESCRIPTION:
XS GIS Cut Line= 2
      1906172.56     13962160.46      1905511.41     13962250.83
#Sta/Elev= 30
  4649.3 1960.88    4659 1956.65  4671.2 1947.44  4686.3  1938.3  4695.4 1934.02
  4698.4 1931.37  4713.6 1922.26  4730.9 1910.55  4752.9    1898  4766.9 1891.15
  4786.9 1880.36  4816.5 1867.74  4828.6  1863.9  4858.9 1856.53  4864.9 1848.74
  4877.1 1838.51  4895.2 1828.83  4960.3 1828.29  5060.3 1828.07    5074    1828
  5074.5  1827.5  5085.8    1828    5092 1829.14  5119.9 1829.12  5149.6 1831.48
  5207.1 1840.71  5222.2 1842.14  5249.5 1842.44  5274.4 1844.31  5316.6 1845.73
#Mann= 6 ,-1 , 0
  4649.3      .1       0  4766.9    .033       0  4960.3      .1       0
  5060.3     .07       0    5074     .05       0  5085.8     .07       0
Bank Sta=5074,5085.8
XS Rating Curve= 0 ,0
Exp/Cntr=0.3,0.1

Type RM Length L Ch R = 1 ,36333   ,28,28,28
BEGIN DESCRIPTION:
Mapping XS 0f5964da
END DESCRIPTION:
XS GIS Cut Line= 4
      1906239.95     13961849.67      1905909.24     13961938.21
      1905774.41     13962004.38      1905486.03     13962201.92
#Sta/Elev= 30
  4529.7 1955.11    4538 1953.77  4575.3 1952.01    4625 1941.59  4643.6 1936.37
  4677.8 1922.91  4710.6 1904.65  4727.5 1897.95  4758.5 1883.49  4774.1 1879.41
  4786.5 1873.45  4795.8 1871.13    4802  1868.1  4833.1 1859.38  4853.3 1852.43
  4857.9 1850.44  4867.2 1840.65  4870.3 1838.42  4883.6 1836.97  4913.7 1828.22
  4964.7 1827.25  4965.2 1826.75  4976.5 1827.25  5027.7  1828.4  5045.9 1834.43
  5060.4 1837.53  5077.6 1837.67  5238.6 1838.61  5289.5 1840.87  5371.8 1846.97
#Mann= 5 ,-1 , 0
  4529.7      .1       0  4853.3    .035       0  4964.7    .035       0
  4976.5    .035       0  5077.6     .07       0
Bank Sta=4964.7,4976.5
XS Rating Curve= 0 ,0
Exp/Cntr=0.3,0.1

Type RM Length L Ch R = 1 ,36305   ,441,441,441
BEGIN DESCRIPTION:
Goat Creek 63.0
END DESCRIPTION:
XS GIS Cut Line= 4
      1906220.04     13961821.89      1905910.11     13961891.34
        1905775.       13961975.      1905474.99     13962175.01
#Sta/Elev= 30
  4527.9 1950.92  4595.7 1940.48  4614.1 1935.44  4644.9 1924.02  4669.5  1913.1
  4687.9 1901.71  4715.6 1886.72  4759.8 1871.01  4798.9 1860.46  4823.2 1854.34
  4838.6 1842.99  4844.7 1841.89  4851.6 1835.22  4873.6 1832.09  4901.9 1823.05
  4908.1 1818.52  4911.6 1817.28  4937.3 1816.92  4937.8 1816.42  4949.1 1816.92
    4983 1817.32  4996.3 1818.88  5014.2  1827.6  5021.4 1829.67  5035.8  1831.1
  5053.8 1831.82  5111.3 1829.42  5182.4 1830.97  5212.5 1835.64    5365 1847.43
#Mann= 5 ,-1 , 0
  4527.9      .1       0  4798.9    .035       0  4937.3    .035       0
  4949.1    .035       0  5111.3     .07       0
Bank Sta=4937.3,4949.1
XS Rating Curve= 0 ,0
Exp/Cntr=0.3,0.1

Type RM Length L Ch R = 1 ,35864   ,451,451,451
BEGIN DESCRIPTION:
Goat Creek 62.0
END DESCRIPTION:
XS GIS Cut Line= 3
      1906165.55     13961614.59        1905525.       13961625.
      1905023.37     13961671.36
#Sta/Elev= 30
  4363.6 1908.98  4411.3 1899.71  4461.1 1884.33  4501.3 1871.95  4525.3 1855.56
  4547.4  1852.4  4597.3 1839.89    4646 1831.95    4705 1826.21  4770.8 1822.89
  4830.6 1822.88  4876.3 1822.12  4898.9 1813.48  4924.3 1810.85  4960.3 1810.03
  4966.3 1809.44  4966.7 1807.46  4967.2 1806.96  4978.5 1807.46  5011.4 1812.26
  5035.5  1823.4  5048.9  1827.1  5074.6 1828.95  5136.5 1838.88  5210.2 1843.97
  5293.5 1846.05  5415.1 1849.13  5460.3  1860.1  5496.4 1874.48    5508 1880.76
#Mann= 10 ,-1 , 0
  4363.6      .1       0  4461.1    .035       0  4547.4     .07       0
    4646      .1       0    4705     .07       0  4830.6      .1       0
  4966.7     .05       0  4978.5      .1       0  5136.5     .07       0
  5293.5      .1       0
Bank Sta=4966.7,4978.5
XS Rating Curve= 0 ,0
Exp/Cntr=0.3,0.1

Type RM Length L Ch R = 1 ,35413   ,455,455,455
BEGIN DESCRIPTION:
Goat Creek 61.0
END DESCRIPTION:
XS GIS Cut Line= 3
      1905925.02       13961225.        1905525.       13961175.
      1905425.03     13961224.99
#Sta/Elev= 30
  4601.2 1846.56  4612.4 1844.56  4627.5 1839.84  4639.6 1837.26  4648.1 1834.56
  4664.2 1831.31  4718.2 1824.88  4745.4  1819.9  4830.1  1813.8  4856.7 1813.02
  4865.8 1813.81  4881.5 1813.67  4914.2 1812.38    4954 1810.15  4974.2  1807.5
  4978.2 1807.64  4984.3 1809.37  4996.4  1809.8  5012.3 1808.92  5019.7  1807.3
  5020.2  1806.8  5031.6  1807.3  5049.2 1808.63  5055.9 1808.06  5060.9 1809.39
  5069.3 1813.64  5074.5 1817.33  5089.4 1830.76  5096.1 1832.11  5116.1  1834.2
#Mann= 3 ,-1 , 0
  4601.2      .1       0  5019.7     .05       0  5031.6      .1       0
Bank Sta=5019.7,5031.6
XS Rating Curve= 0 ,0
Exp/Cntr=0.3,0.1

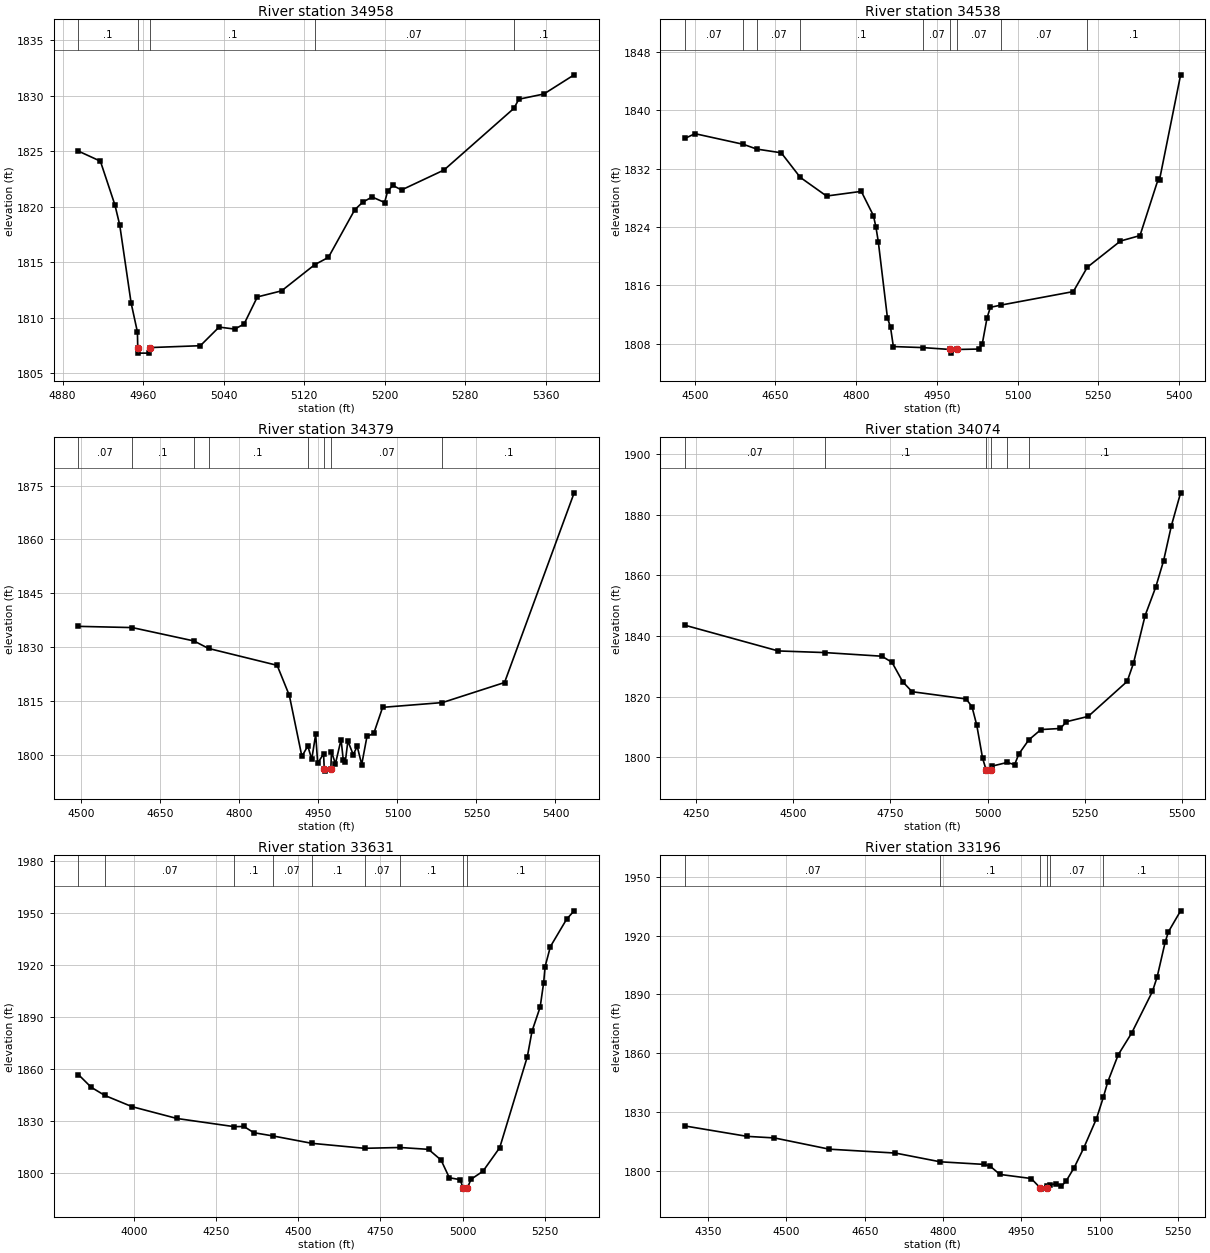
Type RM Length L Ch R = 1 ,34958   ,420,420,420
BEGIN DESCRIPTION:
Goat Creek 60.0
END DESCRIPTION:
XS GIS Cut Line= 3
      1905774.97     13960824.99      1905679.62     13960795.61
      1905299.84     13960895.59
#Sta/Elev= 30
  4895.7 1825.02  4917.6 1824.11    4932 1820.17  4936.8 1818.36  4948.1 1811.33
  4954.4 1808.69  4954.7 1807.29  4955.2 1806.79  4966.2 1806.79  4966.7 1807.29
  5016.9 1807.46  5035.5 1809.14    5051 1808.96  5060.3 1809.41  5073.5 1811.86
  5097.6 1812.41  5130.5 1814.77  5144.1 1815.43  5170.3 1819.73  5178.2 1820.41
  5187.5 1820.88  5199.9 1820.38    5203 1821.42  5208.2 1821.92  5216.7 1821.51
  5258.9 1823.31  5328.3 1828.87  5333.3  1829.7  5358.1 1830.17  5388.2  1831.9
#Mann= 5 ,-1 , 0
  4895.7      .1       0  4954.7     .05       0  4966.7      .1       0
  5130.5     .07       0  5328.3      .1       0
Bank Sta=4954.7,4966.7
XS Rating Curve= 0 ,0
Exp/Cntr=0.3,0.1

Type RM Length L Ch R = 1 ,34538   ,159,159,159
BEGIN DESCRIPTION:
Goat Creek 59.0
END DESCRIPTION:
XS GIS Cut Line= 3
      1905913.06     13960081.29        1905525.       13960425.
        1905125.       13960375.
#Sta/Elev= 30
  4481.6 1836.13  4500.5 1836.79  4590.5 1835.33  4615.2 1834.68  4660.8 1834.17
  4696.2  1830.8    4745 1828.24  4809.6 1828.88  4832.2 1825.55  4836.7 1824.03
  4841.2    1822  4858.2 1811.54  4863.9 1810.27  4869.2  1807.6  4923.5 1807.46
  4975.2  1807.2  4975.7  1806.7  4987.6  1807.2  5028.3 1807.26  5034.4 1807.95
  5043.4 1811.56  5049.5 1812.98  5069.4 1813.29  5203.7 1815.14  5229.7 1818.48
  5291.3 1822.07  5327.6 1822.82  5361.3 1830.53  5363.9 1830.47  5403.1 1844.86
#Mann= 9 ,-1 , 0
  4481.6     .07       0  4590.5      .1       0  4615.2     .07       0
  4696.2      .1       0  4923.5     .07       0  4975.2     .05       0
  4987.6     .07       0  5069.4     .07       0  5229.7      .1       0
Bank Sta=4975.2,4987.6
XS Rating Curve= 0 ,0
Exp/Cntr=0.3,0.1

Type RM Length L Ch R = 1 ,34379   ,305,305,305
BEGIN DESCRIPTION:
Goat Creek 58.1
END DESCRIPTION:
XS GIS Cut Line= 4
      1905926.11     13960053.36      1905546.36     13960230.22
      1905420.49     13960324.62      1905055.95      13960347.4
#Sta/Elev= 30
    4494  1835.8  4596.3 1835.46  4713.4 1831.74  4741.2 1829.65  4871.5 1824.95
  4894.7 1816.55  4918.5 1799.59  4929.7 1802.48  4937.2  1798.8  4944.7 1805.74
  4948.5 1797.65  4959.7 1800.34    4961 1795.99  4961.5 1795.49  4973.4 1795.99
  4974.7 1800.91  4982.2 1797.54  4992.9 1804.28  4997.2 1798.45    5001 1798.13
  5005.8  1803.9    5016 1800.06  5023.5 1802.41  5032.1 1797.33  5042.1 1805.15
    5055    1806  5071.8 1813.25  5185.4 1814.58  5303.3 1820.16  5435.5 1872.98
#Mann= 8 ,-1 , 0
    4494     .07       0  4596.3      .1       0  4713.4     .07       0
  4741.2      .1       0  4929.7     .07       0    4961     .05       0
  4973.4     .07       0  5185.4      .1       0
Bank Sta=4961,4973.4
XS Rating Curve= 0 ,0
Exp/Cntr=0.3,0.1

Type RM Length L Ch R = 1 ,34074   ,443,443,443
BEGIN DESCRIPTION:
Goat Creek 58.0
END DESCRIPTION:
XS GIS Cut Line= 3
      1906194.63     13959942.22        1905425.       13960025.
      1905024.98     13960325.02
#Sta/Elev= 30
  4221.8 1843.54  4461.9 1835.05  4581.4 1834.51  4728.1 1833.31  4754.2  1831.3
  4781.7  1824.9  4805.8  1821.6  4944.7 1819.21  4959.8 1816.64  4972.1 1810.53
  4986.9 1799.74  4995.9  1795.9  4996.4  1795.4  5008.3  1795.9    5011 1797.04
  5050.5 1798.27  5069.3 1797.52    5080 1801.02  5105.7  1805.7  5137.1 1809.12
  5187.1 1809.47  5202.2 1811.69  5258.5 1813.46  5358.6 1825.01  5374.7 1830.98
  5404.7 1846.74  5432.1 1856.16  5452.1  1864.8  5472.2 1876.38  5495.9 1887.21
#Mann= 6 ,-1 , 0
  4221.8     .07       0  4581.4      .1       0  4995.9     .05       0
  5008.3      .1       0  5050.5     .07       0  5105.7      .1       0
Bank Sta=4995.9,5008.3
XS Rating Curve= 0 ,0
Exp/Cntr=0.3,0.1

Type RM Length L Ch R = 1 ,33631   ,435,435,435
BEGIN DESCRIPTION:
Goat Creek 57.0
END DESCRIPTION:
XS GIS Cut Line= 4
       1906333.5     13959745.22      1905636.95     13959637.73
        1905175.       13959675.       1904835.5     13959668.61
#Sta/Elev= 30
  3831.4 1857.04  3870.5 1849.68  3912.2 1844.94  3994.9 1838.48  4131.5 1831.67
  4305.6 1826.96  4334.9 1827.07  4365.2 1823.47  4422.9 1821.62  4541.2 1817.36
  4701.8 1814.48  4809.3 1814.95  4896.4 1813.88  4934.5 1807.69  4959.6  1797.5
  4992.7  1796.4  5001.5 1791.44    5002 1790.94    5014 1791.44  5025.7 1796.64
  5061.8 1801.25  5112.8 1814.83  5196.8 1867.31  5211.1 1882.06  5235.8 1895.93
  5246.4 1909.95  5250.8 1919.26    5267 1930.82  5316.5 1946.67  5339.2 1951.43
#Mann= 9 ,-1 , 0
  3831.4      .1       0  3912.2     .07       0  4305.6      .1       0
  4422.9     .07       0  4541.2      .1       0  4701.8     .07       0
  4809.3      .1       0  5001.5     .05       0    5014      .1       0
Bank Sta=5001.5,5014
XS Rating Curve= 0 ,0
Exp/Cntr=0.3,0.1

Type RM Length L Ch R = 1 ,33196   ,467,467,467
BEGIN DESCRIPTION:
Goat Creek 56.0
END DESCRIPTION:
XS GIS Cut Line= 3
      1905864.47      13959352.9        1905175.       13959275.
      1904925.01       13959325.
#Sta/Elev= 30
  4305.7 1822.78    4425 1817.45  4477.3 1816.65    4582 1810.91  4708.8 1808.91
  4794.4 1804.45  4877.9 1803.13    4890 1802.24  4908.6    1798  4968.5 1795.91
  4986.3 1790.98  4986.8 1790.48  4998.8 1790.98  4999.4 1791.97  5005.2 1792.78
  5016.6 1793.23  5026.2 1791.91  5035.4  1794.6  5050.7 1801.42    5069 1811.45
  5093.5 1826.53  5106.5 1837.34  5114.9 1845.16  5135.1 1859.18  5160.8 1870.26
  5200.6 1891.56  5209.7 1899.08    5225 1916.87  5231.2 1922.06  5254.5 1932.75
#Mann= 6 ,-1 , 0
  4305.7     .07       0  4794.4      .1       0  4986.3     .05       0
  4998.8      .1       0  5005.2     .07       0  5106.5      .1       0
Bank Sta=4986.3,4998.8
XS Rating Curve= 0 ,0
Exp/Cntr=0.3,0.1