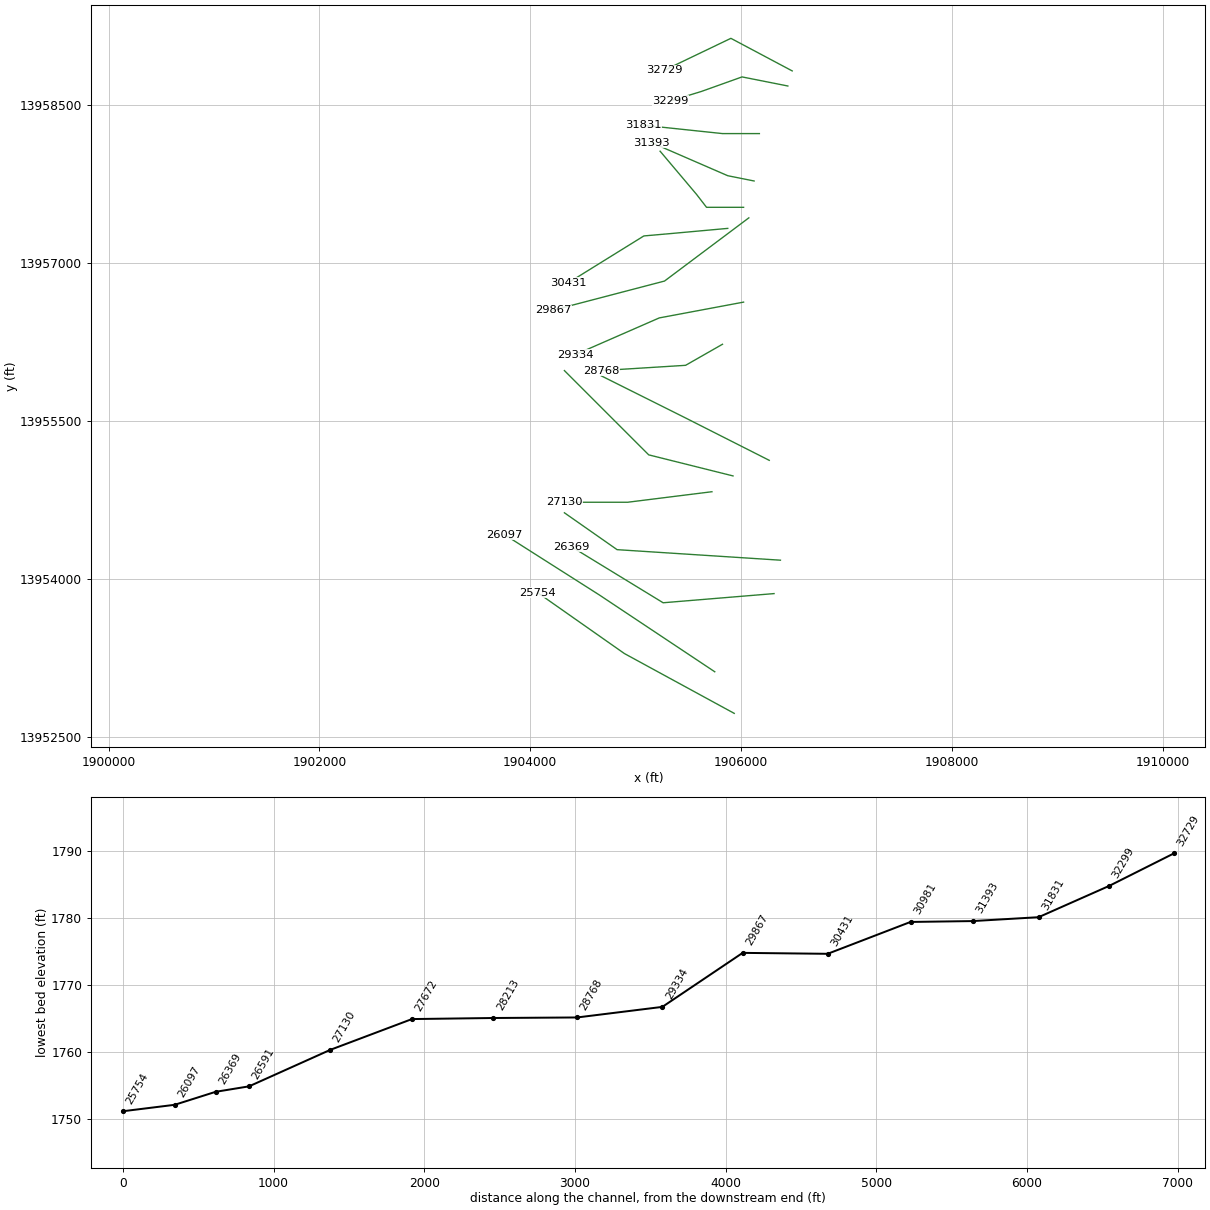
HEC-RAS study Goat Creek.prj: Goat Creek Base Level Engineering

--- Goat Creek.g01 (geometry) --- (continued)

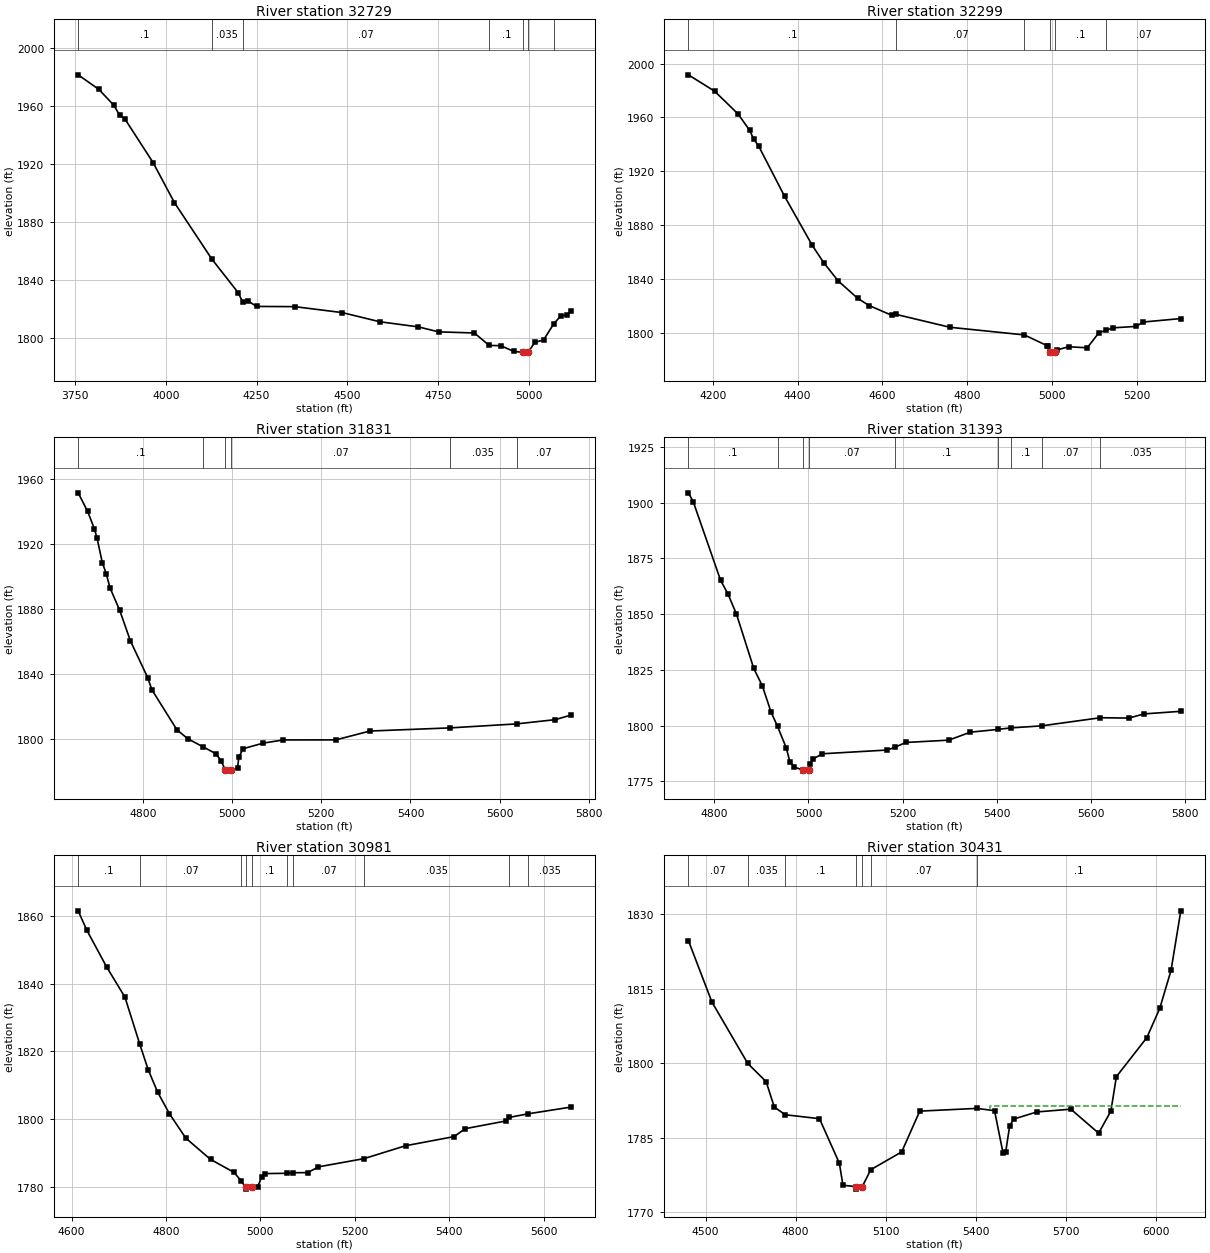
Type RM Length L Ch R = 1 ,32729   ,430,430,430
BEGIN DESCRIPTION:
Goat Creek 55.0
END DESCRIPTION:
XS GIS Cut Line= 4
      1906486.39     13958819.97      1905904.78     13959129.24
        1905375.       13958875.      1905274.96     13958824.98
#Sta/Elev= 30
  3757.8 1981.66  3814.8 1971.62  3855.8 1960.78  3872.3 1953.83  3886.3 1951.37
  3964.5 1921.11  4023.4 1893.46  4126.8 1854.45  4198.9 1831.44  4211.7 1824.94
  4227.5 1825.49  4249.9 1821.87  4355.2 1821.73  4486.3 1817.62  4589.4 1811.32
  4695.9 1807.78  4751.8 1804.34  4850.8 1803.55  4891.5 1794.97  4923.9 1794.79
  4958.7 1790.87  4986.1 1790.16  4986.6 1789.66  4998.7 1790.16  5017.1 1797.01
  5041.7  1798.8  5070.1 1810.06  5089.2 1815.37  5106.5 1816.12    5116 1818.71
#Mann= 7 ,-1 , 0
  3757.8      .1       0  4126.8    .035       0  4211.7     .07       0
  4891.5      .1       0  4986.1     .05       0  4998.7      .1       0
  5070.1    .035       0
Bank Sta=4986.1,4998.7
XS Rating Curve= 0 ,0
Exp/Cntr=0.3,0.1

Type RM Length L Ch R = 1 ,32299   ,468,468,468
BEGIN DESCRIPTION:
Goat Creek 54.0
END DESCRIPTION:
XS GIS Cut Line= 4
      1906445.44     13958676.72      1906010.64     13958763.01
        1905625.       13958625.      1905330.97     13958535.25
#Sta/Elev= 30
  4142.8 1991.62  4204.5 1979.48  4259.6 1962.63  4287.1  1950.4  4296.3 1944.08
  4308.5 1938.58  4369.7  1901.2  4434.7  1864.9  4461.4 1852.13  4495.8 1838.44
  4541.6 1825.57  4568.5 1820.19  4621.9 1812.94  4632.9 1813.54  4758.9 1804.02
  4934.4 1798.34  4988.1 1790.35  4990.5 1789.83  4994.7  1785.3  4995.2  1784.8
  5007.4  1785.3  5010.4 1787.07  5038.6 1789.53  5082.6 1788.77  5110.5 1800.08
  5127.6 1801.72  5142.2 1803.55  5198.6 1804.69  5213.8 1807.89  5303.1 1810.49
#Mann= 6 ,-1 , 0
  4142.8      .1       0  4632.9     .07       0  4934.4      .1       0
  4994.7     .05       0  5007.4      .1       0  5127.6     .07       0
Bank Sta=4994.7,5007.4
XS Rating Curve= 0 ,0
Exp/Cntr=0.3,0.1

Type RM Length L Ch R = 1 ,31831   ,438,438,438
BEGIN DESCRIPTION:
Goat Creek 53.0
END DESCRIPTION:
XS GIS Cut Line= 3
      1906174.96       13958225.        1905825.       13958225.
      1905075.64     13958304.27
#Sta/Elev= 30
  4655.3 1951.63  4676.4 1940.26  4691.4 1929.64  4697.4 1923.98  4709.4 1908.62
  4718.4 1901.61  4726.6 1893.13  4748.4 1879.21  4772.4 1860.38  4811.4 1837.59
  4820.4 1830.33  4876.6 1805.58  4901.4 1800.01  4935.5 1795.06  4964.4 1790.79
  4976.4 1786.18    4985 1780.63  4985.5 1780.13  4997.7 1780.63  5012.4 1782.19
  5015.4 1788.55  5024.5  1793.9  5069.7 1797.38    5115 1799.35  5232.6 1799.38
  5309.3 1804.84  5489.1 1806.78  5637.7 1809.23  5724.4 1811.85  5758.8 1814.58
#Mann= 6 ,-1 , 0
  4655.3      .1       0  4935.5     .07       0    4985     .05       0
  4997.7     .07       0  5489.1    .035       0  5637.7     .07       0
#XS Ineff= 2 , 0
                         5122.48         1799.35
Permanent Ineff=
       F       F
Bank Sta=4985,4997.7
XS Rating Curve= 0 ,0
Exp/Cntr=0.3,0.1

Type RM Length L Ch R = 1 ,31393   ,412,412,412
BEGIN DESCRIPTION:
Goat Creek 52.0
END DESCRIPTION:
XS GIS Cut Line= 3
      1906124.97     13957775.01        1905875.       13957825.
      1905150.17      13958139.9
#Sta/Elev= 30
  4745.1 1904.42  4755.4 1900.43  4813.5 1865.13  4828.8 1859.18  4847.2 1849.98
  4883.9  1825.6  4902.2 1817.72  4920.6 1806.03  4934.3 1799.63  4953.1 1789.83
  4960.3 1783.86  4969.5 1781.41  4987.7 1780.05  4988.2 1779.55  5000.4 1780.05
  5003.7 1782.71  5009.9 1785.01  5029.6 1787.34  5166.9 1789.01  5183.6 1790.24
  5206.2  1792.4  5297.8 1793.45  5343.6 1797.03  5401.6 1798.25  5428.9 1798.93
  5494.8 1799.86  5619.7 1803.51  5680.5 1803.36  5712.1 1805.22  5790.3 1806.39
#Mann= 9 ,-1 , 0
  4745.1      .1       0  4934.3     .07       0  4987.7     .05       0
  5000.4     .07       0  5183.6      .1       0  5401.6     .07       0
  5428.9      .1       0  5494.8     .07       0  5619.7    .035       0
Bank Sta=4987.7,5000.4
XS Rating Curve= 0 ,0
Exp/Cntr=0.3,0.1

Type RM Length L Ch R = 1 ,30981   ,550,550,550
BEGIN DESCRIPTION:
Goat Creek 51.0
END DESCRIPTION:
XS GIS Cut Line= 4
      1906025.05       13957525.       1905673.6       13957525.
      1905579.04     13957647.56      1905232.93     13958057.95
#Sta/Elev= 30
  4614.1 1861.47  4632.2 1855.81  4674.2 1844.98  4713.2 1836.02  4744.7 1822.12
  4762.5 1814.61  4782.2 1808.09  4807.5 1801.63  4842.2 1794.45  4894.5 1788.18
  4944.2 1784.37  4959.9 1781.77  4968.8 1779.92  4969.3 1779.42  4981.5 1779.92
  4994.3 1780.03  5002.9  1783.1  5009.4    1784  5057.1 1784.09  5068.7 1784.25
  5100.4 1784.29  5123.2 1785.99  5219.6 1788.41  5307.6 1792.21  5410.6 1794.91
  5433.9 1797.24  5519.6  1799.5  5527.2 1800.57    5568 1801.64  5657.2 1803.59
#Mann= 10 ,-1 , 0
  4614.1      .1       0  4744.7     .07       0  4959.9      .1       0
  4968.8     .05       0  4981.5      .1       0  5057.1    .035       0
  5068.7     .07       0  5219.6    .035       0  5527.2     .07       0
    5568    .035       0
Bank Sta=4968.8,4981.5
XS Rating Curve= 0 ,0
Exp/Cntr=0.3,0.1

Type RM Length L Ch R = 1 ,30431   ,564,564,564
BEGIN DESCRIPTION:
Goat Creek 50.0
END DESCRIPTION:
XS GIS Cut Line= 4
      1905874.99       13957325.        1905325.       13957275.
      1905079.13     13957253.35      1904363.44     13956809.36
#Sta/Elev= 30
  4442.4 1824.73  4520.8 1812.34  4640.3 1799.97  4701.6  1796.3  4728.7  1791.2
  4765.1 1789.64  4879.3 1788.85  4945.6 1779.89  4957.6 1775.44  5001.8 1775.16
  5002.3 1774.66  5021.9 1775.16  5050.2 1778.57  5153.4 1782.16  5213.6 1790.37
  5403.8 1790.92  5462.9 1790.46  5491.2 1781.92  5499.9 1782.07    5513  1787.3
  5526.1 1788.76  5604.5 1790.21  5717.2 1790.76  5809.8 1785.93  5850.7 1790.38
    5869 1797.31  5970.5 1805.17  6013.7 1811.08  6051.1  1818.7  6083.7 1830.71
#Mann= 7 ,-1 , 0
  4442.4     .07       0  4640.3    .035       0  4765.1      .1       0
  5001.8     .05       0  5021.9      .1       0  5050.2     .07       0
  5403.8      .1       0
#XS Ineff= 2 , 0
                         5446.51         1791.43
Permanent Ineff=
       F       F
Bank Sta=5001.8,5021.9
XS Rating Curve= 0 ,0
Exp/Cntr=0.3,0.1

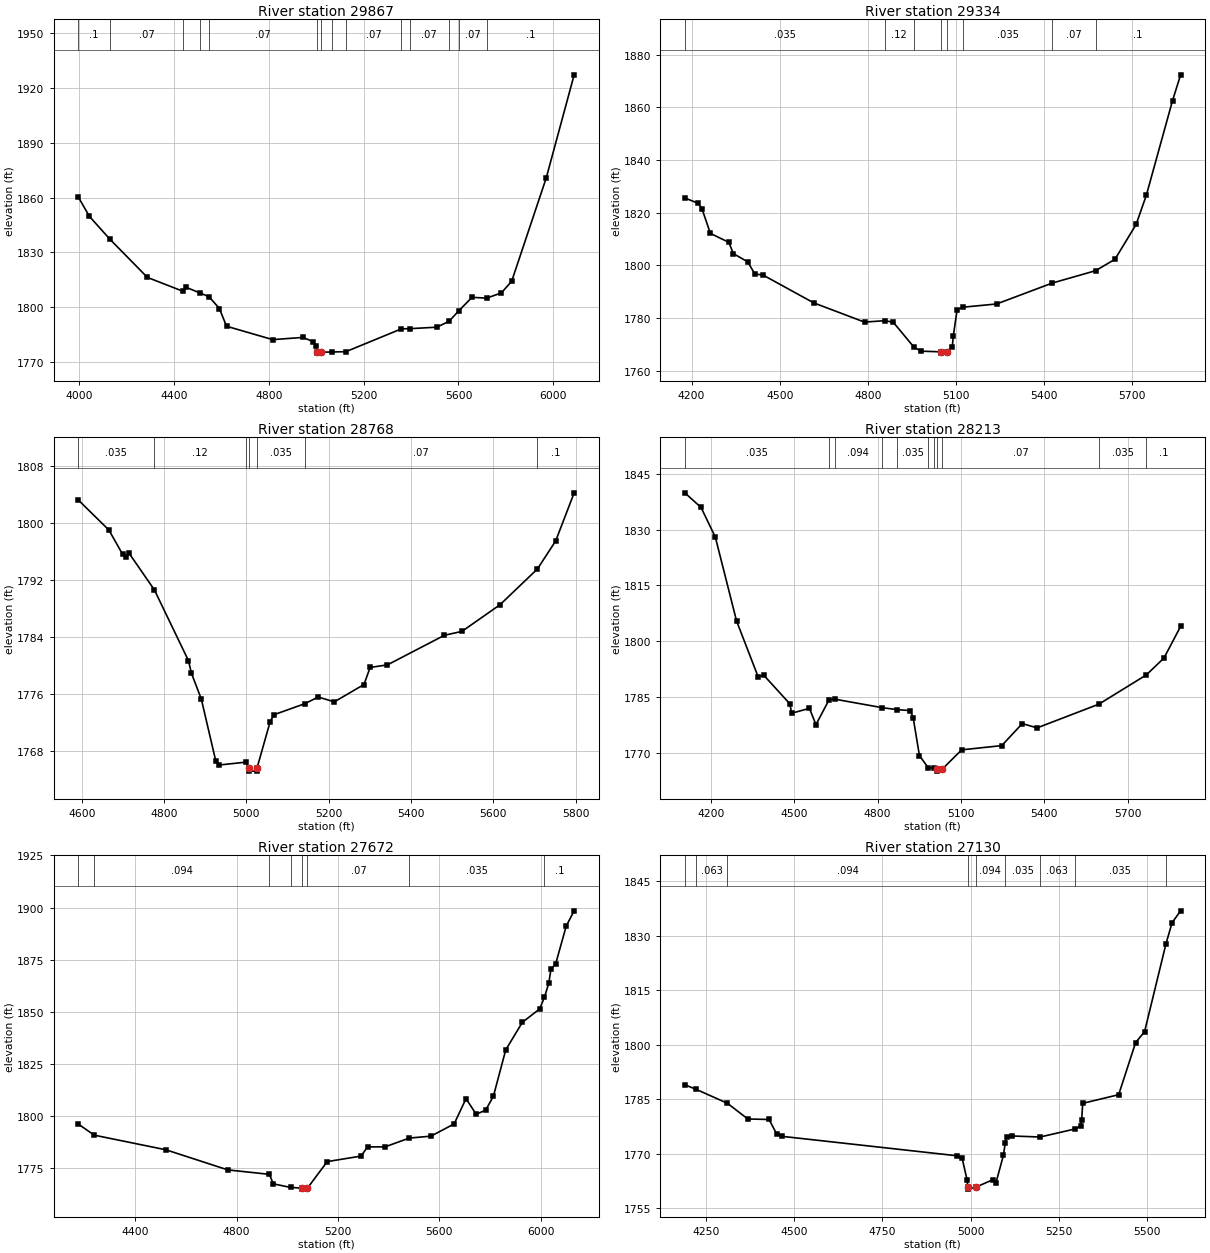
Type RM Length L Ch R = 1 ,29867   ,533,533,533
BEGIN DESCRIPTION:
Goat Creek 49.0
END DESCRIPTION:
XS GIS Cut Line= 3
      1906074.99       13957425.        1905275.       13956825.
      1904218.95     13956548.67
#Sta/Elev= 30
  3996.4 1860.26  4043.1 1849.69  4129.4  1837.2  4287.8 1816.26  4439.9 1808.57
  4452.4 1810.75  4510.3 1807.72  4547.9 1805.68  4591.5 1799.23  4621.5 1789.53
  4816.5 1782.19    4944  1783.4  4985.9 1781.16  5000.4 1778.59    5002  1775.3
  5002.5  1774.8  5022.1  1775.3  5067.4 1775.43  5125.1  1775.6  5359.1 1788.09
  5393.6 1788.19  5507.9    1789  5559.7 1792.15  5602.5 1798.14  5657.2 1805.37
  5718.4  1804.9  5781.2 1807.79  5824.6 1814.22  5970.4 1870.82    6088 1927.21
#Mann= 14 ,-1 , 0
  3996.4      .1       0  4129.4     .07       0  4439.9    .035       0
  4510.3      .1       0  4547.9     .07       0    5002     .05       0
  5022.1     .07       0  5067.4    .035       0  5125.1     .07       0
  5359.1    .035       0  5393.6     .07       0  5559.7      .1       0
  5602.5     .07       0  5718.4      .1       0
Bank Sta=5002,5022.1
XS Rating Curve= 0 ,0
Exp/Cntr=0.3,0.1

Type RM Length L Ch R = 1 ,29334   ,566,566,566
BEGIN DESCRIPTION:
Goat Creek 48.0
END DESCRIPTION:
XS GIS Cut Line= 3
      1906025.04     13956625.01        1905225.       13956475.
      1904424.99       13956125.
#Sta/Elev= 30
  4176.9  1825.6  4222.9 1823.55  4235.2 1821.52    4264 1812.15  4326.8 1808.76
    4342 1804.49  4390.9 1801.37  4415.3 1796.74  4442.8 1796.37  4616.1 1785.77
  4788.4  1778.5  4856.5 1779.03    4886 1778.48  4956.3 1769.04  4981.1 1767.47
  5047.7 1767.23  5048.2 1766.73  5067.8 1767.23  5087.2 1769.19  5090.5 1773.19
  5103.6 1783.26  5124.3 1784.16  5237.9 1785.38  5427.3 1793.31  5574.6    1798
  5640.6 1802.32  5712.7 1815.56  5747.6 1826.69  5836.5 1862.52  5864.1 1872.31
#Mann= 8 ,-1 , 0
  4176.9    .035       0  4856.5     .12       0  4956.3    .035       0
  5047.7    .035       0  5067.8    .035       0  5124.3    .035       0
  5427.3     .07       0  5574.6      .1       0
Bank Sta=5047.7,5067.8
XS Rating Curve= 0 ,0
Exp/Cntr=0.3,0.1

Type RM Length L Ch R = 1 ,28768   ,555,555,555
BEGIN DESCRIPTION:
Goat Creek 47.0
END DESCRIPTION:
XS GIS Cut Line= 3
      1905825.03     13956225.02        1905475.       13956025.
        1904675.       13955975.
#Sta/Elev= 30
  4591.8 1803.19  4665.9 1798.99  4699.3 1795.59  4707.3 1795.17  4715.5 1795.69
  4776.7 1790.57  4859.4 1780.65  4866.4 1778.92  4890.6 1775.26  4925.8 1766.56
  4932.4    1766  4999.1 1766.41  5006.2 1765.65  5006.7 1765.15  5025.8 1765.15
  5026.3 1765.65  5057.3 1771.98  5066.4 1773.05  5142.5 1774.62  5174.6 1775.55
  5213.6 1774.87  5285.8  1777.3  5300.8  1779.7  5342.9 1780.06  5481.2 1784.21
  5523.9 1784.76  5616.4  1788.5  5707.3 1793.52  5751.7 1797.46  5796.5  1804.2
#Mann= 7 ,-1 , 0
  4591.8    .035       0  4776.7     .12       0  4999.1    .035       0
  5006.2    .035       0  5026.3    .035       0  5142.5     .07       0
  5707.3      .1       0
Bank Sta=5006.2,5026.3
XS Rating Curve= 0 ,0
Exp/Cntr=0.3,0.1

Type RM Length L Ch R = 1 ,28213   ,541,541,541
BEGIN DESCRIPTION:
Goat Creek 46.0
END DESCRIPTION:
XS GIS Cut Line= 3
       1906268.8     13955122.91        1905475.       13955525.
      1904674.96     13955925.02
#Sta/Elev= 30
  4106.3 1839.88  4164.7 1835.96  4216.3 1827.95  4292.5 1805.45  4369.8  1790.5
  4390.4 1790.86  4484.2 1783.17    4491 1780.63  4554.8 1781.95  4578.3 1777.56
  4625.9  1784.3  4645.5 1784.42  4816.7 1782.13  4870.2  1781.6    4918 1781.34
  4928.1 1779.46  4950.7 1769.24  4982.6 1765.96    5003 1765.95  5012.1 1765.57
  5012.6 1765.07  5032.3 1765.57  5102.6 1770.79  5246.9 1771.93  5320.7 1777.84
  5374.3  1776.7  5596.1 1783.06  5766.9 1790.92  5830.5 1795.45  5890.6 1803.98
#Mann= 11 ,-1 , 0
  4106.3    .035       0  4625.9    .063       0  4645.5    .094       0
  4816.7    .063       0  4870.2    .035       0  4982.6      .1       0
    5003     .07       0  5012.1     .05       0  5032.3     .07       0
  5596.1    .035       0  5766.9      .1       0
#XS Ineff= 2 , 0
         4627.91 1784.23
Permanent Ineff=
       F       F
Bank Sta=5012.1,5032.3
XS Rating Curve= 0 ,0
Exp/Cntr=0.3,0.1

Type RM Length L Ch R = 1 ,27672   ,542,542,542
BEGIN DESCRIPTION:
Goat Creek 45.0
END DESCRIPTION:
XS GIS Cut Line= 3
      1905924.96     13954975.01        1905125.       13955175.
      1904324.97     13955975.03
#Sta/Elev= 30
  4175.9 1796.11  4238.6 1790.81  4521.5 1783.78  4765.8 1774.13  4929.5 1772.01
  4945.1 1767.46    5013 1765.72  5057.7 1765.41  5058.2 1764.91  5079.9 1765.41
  5157.9 1778.12  5291.3 1780.77  5316.8 1785.19  5385.8 1785.19  5481.6 1789.41
  5567.1 1790.33  5658.5 1796.21  5705.2 1808.31  5745.3 1800.88  5782.5 1802.75
  5813.2 1809.43  5862.1 1831.77  5927.7 1844.96  5995.6 1851.36  6014.5 1856.91
  6031.8 1863.76  6040.3 1870.37  6059.2 1873.11  6100.7 1891.19  6131.9 1898.45
#Mann= 8 ,-1 , 0
  4175.9    .035       0  4238.6    .094       0  4929.5      .1       0
    5013     .07       0  5057.7     .05       0  5079.9     .07       0
  5481.6    .035       0  6014.5      .1       0
Bank Sta=5057.7,5079.9
XS Rating Curve= 0 ,0
Exp/Cntr=0.3,0.1

Type RM Length L Ch R = 1 ,27130   ,539,539,539
BEGIN DESCRIPTION:
Goat Creek 44.0
END DESCRIPTION:
XS GIS Cut Line= 3
      1905725.01       13954825.        1904925.       13954725.
      1904325.03       13954725.
#Sta/Elev= 30
  4189.4 1789.01  4220.9 1787.78  4310.5  1783.9  4368.1  1779.6  4428.5 1779.46
  4449.7 1775.51  4464.8 1774.83  4960.6 1769.49  4975.8 1768.86  4989.9 1762.88
  4991.8 1760.81  4992.3 1760.31    5014 1760.81  5062.9  1762.9  5071.9 1762.06
  5092.9 1769.56  5098.3 1773.06  5101.9 1774.54  5116.9 1774.93  5196.9 1774.64
  5295.5 1776.84  5311.9 1777.62  5314.9 1779.27  5317.9  1783.9  5419.9 1786.28
  5467.9  1800.6  5493.3  1803.6  5553.9 1827.71  5571.3 1833.57  5595.6 1836.84
#Mann= 9 ,-1 , 0
  4189.4    .094       0  4220.9    .063       0  4310.5    .094       0
  4991.8     .05       0    5014    .094       0  5098.3    .035       0
  5196.9    .063       0  5295.5    .035       0  5553.9    .063       0
Bank Sta=4991.8,5014
XS Rating Curve= 0 ,0
Exp/Cntr=0.3,0.1

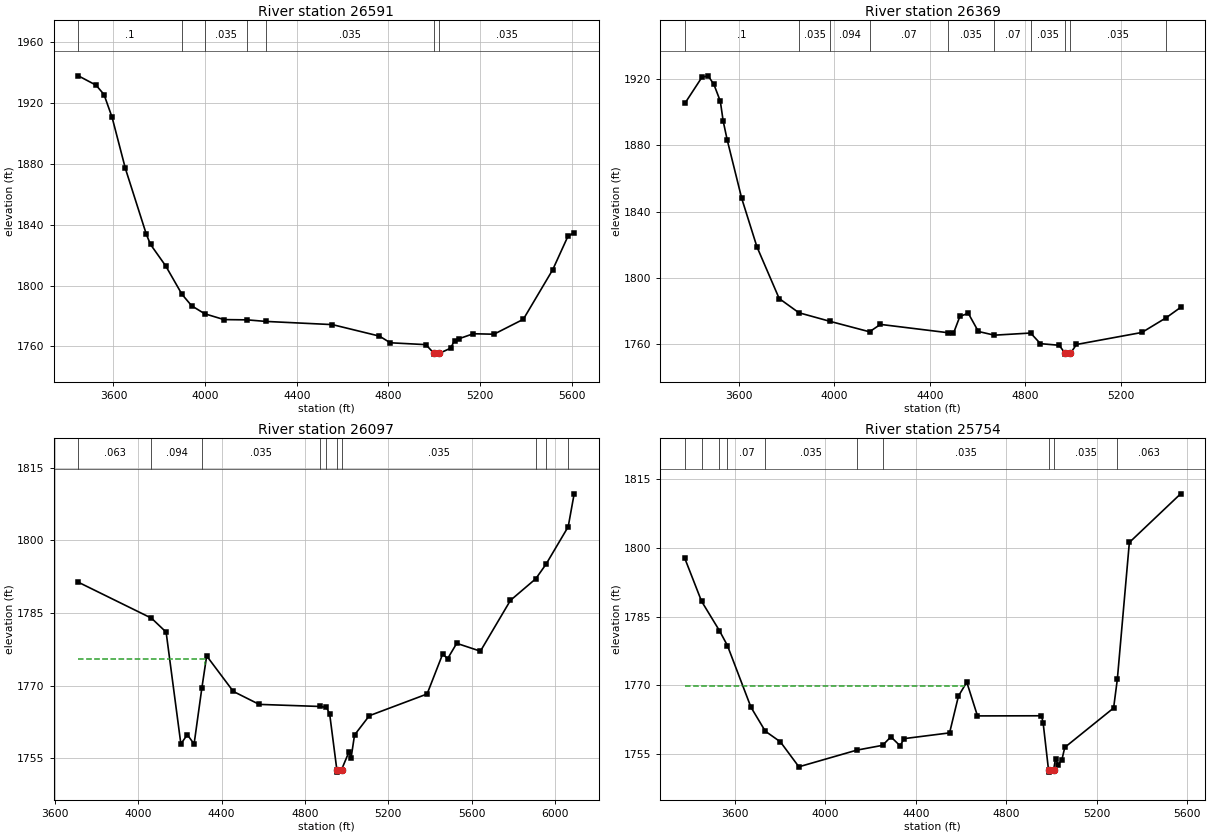
Type RM Length L Ch R = 1 ,26591   ,222,222,222
BEGIN DESCRIPTION:
Goat Creek 43.0
END DESCRIPTION:
XS GIS Cut Line= 3
      1906374.96       13954175.        1904825.       13954275.
      1904325.01     13954624.99
#Sta/Elev= 30
  3446.8 1937.96  3524.2 1931.81  3558.8 1925.67  3594.2 1910.59    3652 1877.04
  3743.7 1833.63  3761.7 1827.03  3827.8 1812.95    3899 1794.22  3941.2 1786.67
  3998.1 1781.42  4082.6 1777.58  4183.8  1777.4  4263.7 1776.39  4555.3 1774.28
  4760.7 1766.71  4807.9 1762.33  4963.2  1761.1  4998.8 1755.36  4999.3 1754.86
  5021.1 1755.36  5070.9 1758.72  5088.2 1763.78  5106.5 1764.93  5170.3 1768.27
  5260.3 1767.96  5388.5 1777.78  5516.7 1810.38    5583 1832.35  5610.3 1834.75
#Mann= 7 ,-1 , 0
  3446.8      .1       0    3899     .07       0  3998.1    .035       0
  4183.8    .063       0  4263.7    .035       0  4998.8    .035       0
  5021.1    .035       0
Bank Sta=4998.8,5021.1
XS Rating Curve= 0 ,0
Exp/Cntr=0.3,0.1

Type RM Length L Ch R = 1 ,26369   ,272,272,272
BEGIN DESCRIPTION:
Mapping XS 72fcc320
END DESCRIPTION:
XS GIS Cut Line= 3
      1906314.12     13953857.87      1905261.88     13953770.81
      1904389.24     13954304.42
#Sta/Elev= 30
  3373.2  1905.3  3445.1 1921.15  3470.9    1922  3495.2 1916.83  3522.1 1906.67
  3534.1  1894.7  3550.8 1883.43  3611.9 1847.99  3675.6 1818.81  3768.9 1787.59
  3851.5 1779.02  3983.1 1773.78  4147.6 1767.52  4193.4 1771.98  4475.8 1766.98
  4499.6 1766.64  4526.5 1776.83  4561.7 1778.68  4603.9 1767.71    4671 1765.48
  4823.1 1766.77    4864 1760.36  4942.6 1759.38  4967.7 1754.54  4968.2 1754.04
    4990 1754.54  5015.3 1759.86  5289.6 1767.12  5391.3    1776  5451.9 1782.25
#Mann= 10 ,-1 , 0
  3373.2      .1       0  3851.5    .035       0  3983.1    .094       0
  4147.6     .07       0  4475.8    .035       0    4671     .07       0
  4823.1    .035       0  4967.7    .035       0    4990    .035       0
  5391.3    .063       0
#XS Ineff= 2 , 0
         4556.85 1777.79
Permanent Ineff=
       F       F
Bank Sta=4967.7,4990
XS Rating Curve= 0 ,0
Exp/Cntr=0.3,0.1

Type RM Length L Ch R = 1 ,26097   ,343,343,343
BEGIN DESCRIPTION:
Goat Creek 42.0
END DESCRIPTION:
XS GIS Cut Line= 3
       1905751.6      13953115.8      1904655.57     13953845.58
      1903757.99     13954416.82
#Sta/Elev= 30
  3712.2 1791.35  4063.4 1783.92  4133.7 1781.04  4204.5 1757.93  4235.6 1759.84
    4268  1757.9  4305.4 1769.51  4328.4 1776.12  4456.3 1768.78  4580.7  1766.1
  4871.9 1765.67  4903.7 1765.48    4919 1764.12  4953.4  1752.6  4953.9  1752.1
    4976  1752.6  5011.1 1756.22  5021.9 1755.03  5038.3 1759.77  5109.4 1763.76
  5386.8 1768.25  5461.4 1776.49  5485.4 1775.56    5529 1778.72  5642.8  1777.1
  5787.1 1787.61  5908.4 1792.06  5957.7 1795.06  6064.3 1802.82  6092.9 1809.62
#Mann= 10 ,-1 , 0
  3712.2    .063       0  4063.4    .094       0  4305.4    .035       0
  4871.9    .063       0  4903.7    .035       0  4953.4    .035       0
    4976    .035       0  5908.4      .1       0  5957.7    .035       0
  6064.3      .1       0
#XS Ineff= 2 , 0
         4321.71  1775.5
Permanent Ineff=
       F       F
Bank Sta=4953.4,4976
XS Rating Curve= 0 ,0
Exp/Cntr=0.3,0.1

Type RM Length L Ch R = 1 ,25754   ,251,251,251
BEGIN DESCRIPTION:
Mapping XS 52907d34
END DESCRIPTION:
XS GIS Cut Line= 3
      1905936.46     13952720.72      1904894.34     13953288.63
       1904072.3      13953865.9
#Sta/Elev= 30
  3378.7 1797.66  3452.7 1788.32  3531.9 1781.91    3567 1778.69  3671.1 1765.26
  3734.4 1760.05  3800.9 1757.74  3882.9  1752.3  4138.4 1755.92  4252.7 1756.97
  4289.5 1758.82  4330.1 1756.87  4348.2 1758.43  4548.9 1759.68  4588.2  1767.7
  4624.9 1770.72  4672.2 1763.37  4954.9  1763.4  4962.2 1761.93  4986.1 1751.64
  4986.6 1751.14  5008.7 1751.64  5017.2 1754.08  5028.2 1752.79  5044.8 1753.73
    5058 1756.52  5273.8 1765.09  5290.3 1771.34  5343.4 1801.11    5570 1811.69
#Mann= 10 ,-1 , 0
  3378.7    .035       0  3452.7     .07       0  3531.9    .035       0
    3567     .07       0  3734.4    .035       0  4138.4    .063       0
  4252.7    .035       0  4986.1    .035       0  5008.7    .035       0
  5290.3    .063       0
#XS Ineff= 2 , 0
          4612.4 1769.95
Permanent Ineff=
       F       F
Bank Sta=4986.1,5008.7
XS Rating Curve= 0 ,0
Exp/Cntr=0.3,0.1