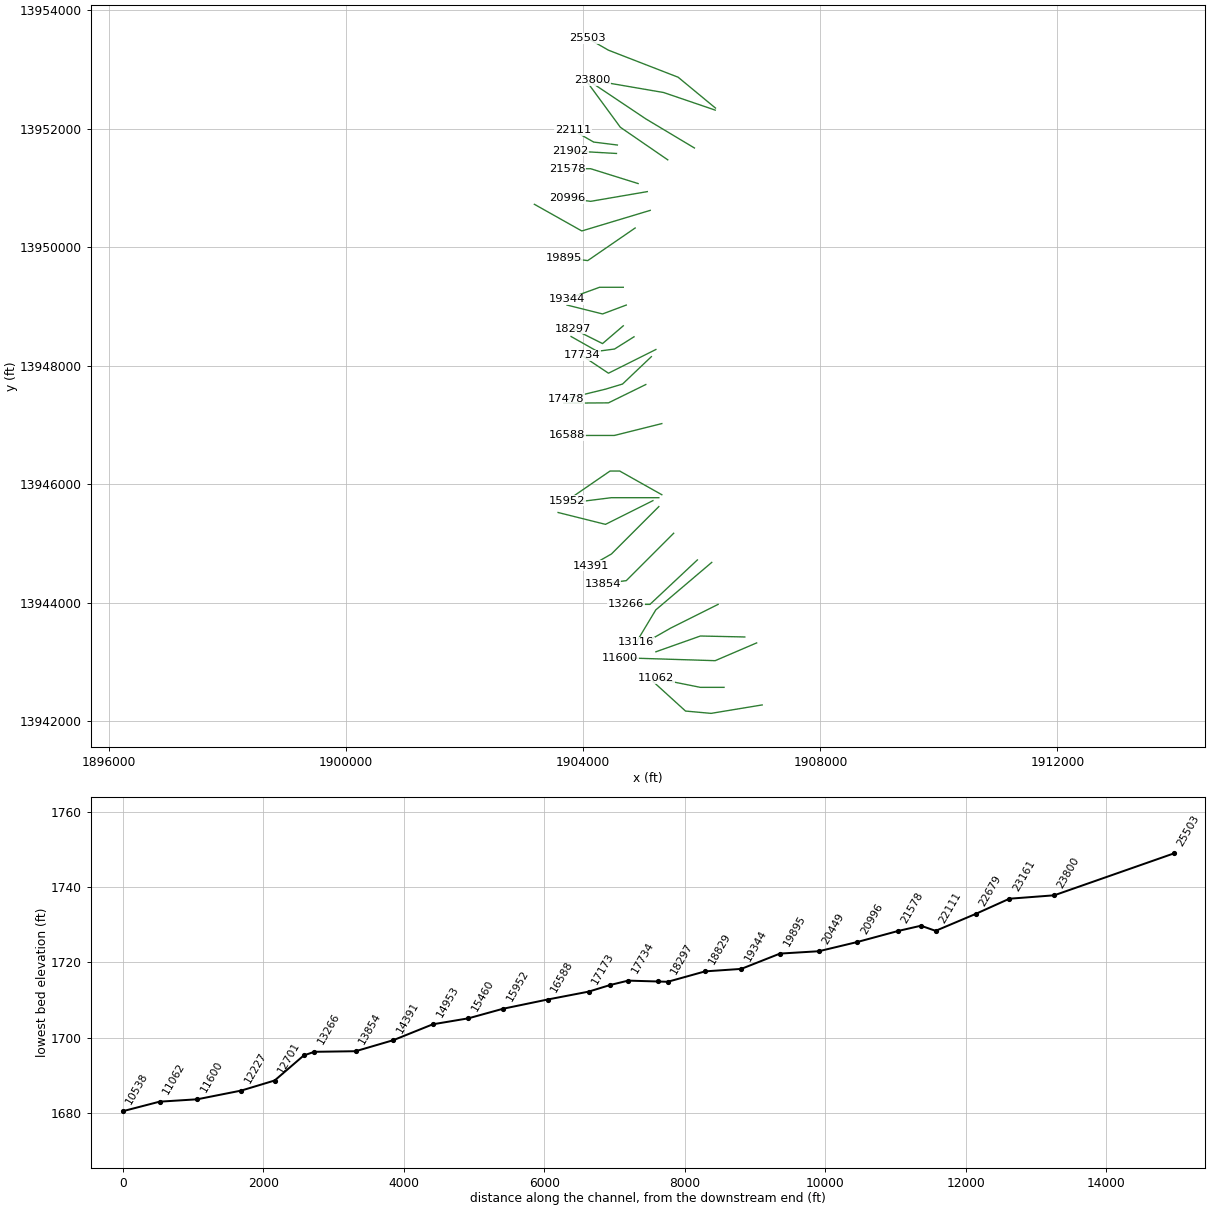
HEC-RAS study Goat Creek.prj: Goat Creek Base Level Engineering

--- Goat Creek.g01 (geometry) --- (continued)

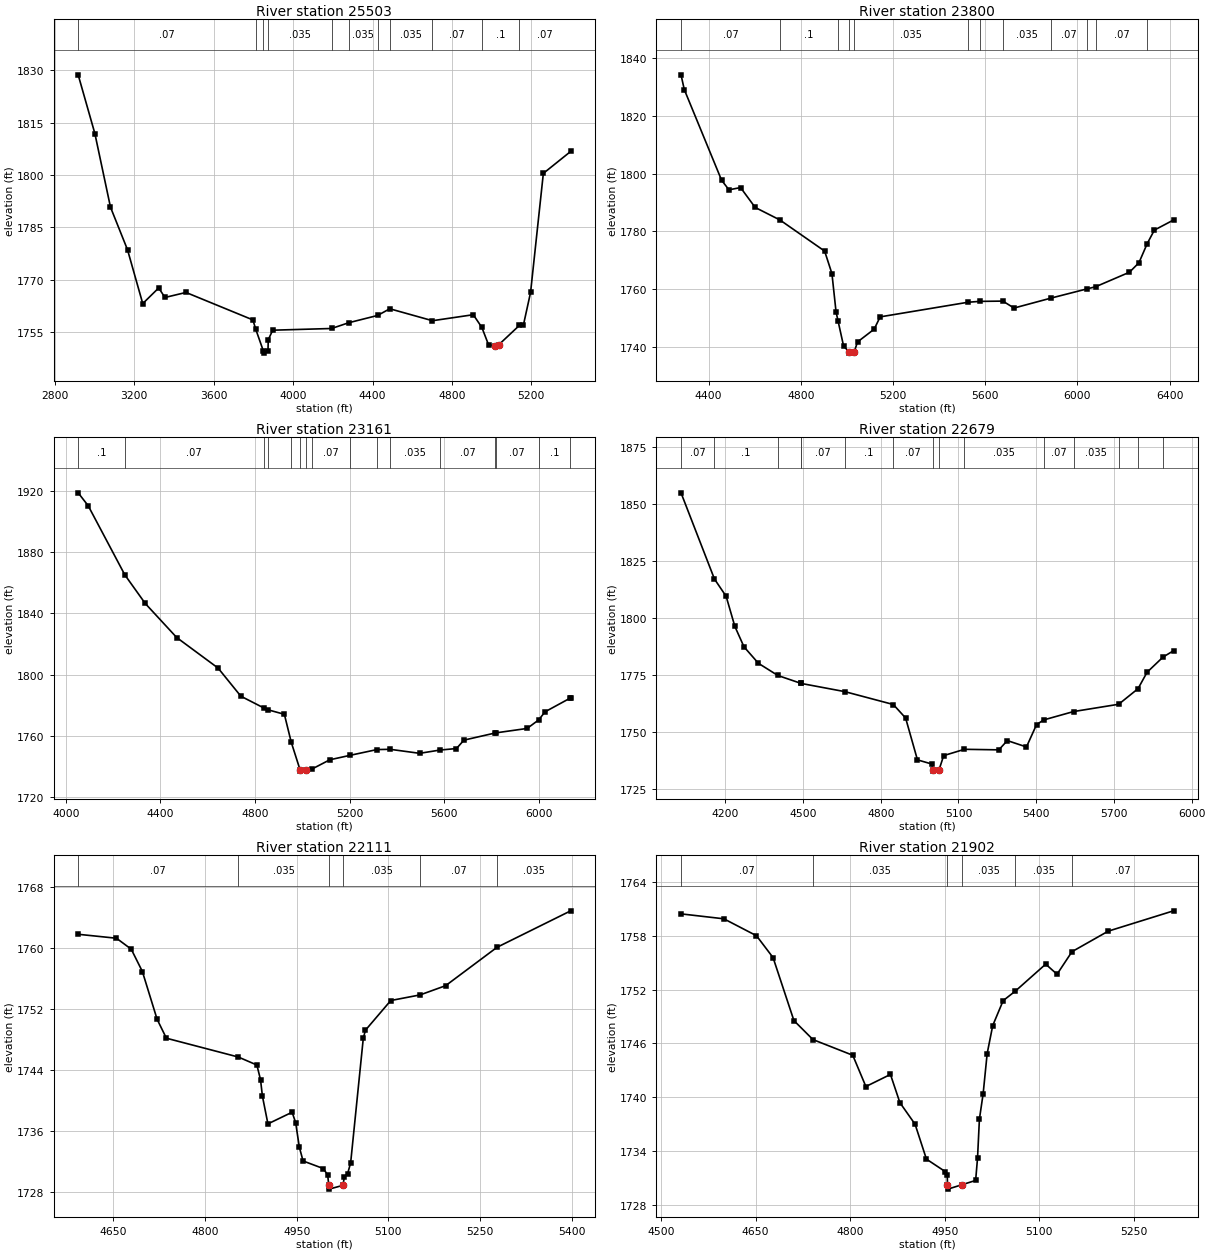
Type RM Length L Ch R = 1 ,25503   ,1703,1703,1703
BEGIN DESCRIPTION:
Goat Creek 41.0
END DESCRIPTION:
XS GIS Cut Line= 4
      1906230.53     13952348.26      1905600.25      13952868.8
        1904425.       13953325.      1904075.04     13953524.98
#Sta/Elev= 30
  2917.2 1828.73  3001.3 1811.91    3080  1790.8  3165.9 1778.58  3242.5 1763.17
  3322.9 1767.65  3354.4 1764.92  3460.4 1766.36  3797.4 1758.49  3811.4 1755.88
  3850.8 1749.47  3851.3 1748.97  3873.4 1749.47  3874.7  1752.8  3897.2 1755.54
  4193.7 1756.03  4280.7 1757.69  4425.2 1759.76  4487.1 1761.68    4702 1758.26
  4907.7 1759.98  4950.8 1756.34  4984.9  1751.3  5014.8 1751.15  5034.9 1751.31
  5139.6  1756.9  5160.4 1757.08  5196.2 1766.36  5260.6 1800.49  5398.4 1806.78
#Mann= 11 ,-1 , 0
  2917.2     .07       0  3811.4    .035       0  3850.8     .05       0
  3873.4    .035       0  4193.7    .063       0  4280.7    .035       0
  4425.2    .063       0  4487.1    .035       0    4702     .07       0
  4950.8      .1       0  5139.6     .07       0
Bank Sta=5014.8,5034.9
XS Rating Curve= 0 ,0
Exp/Cntr=0.3,0.1

Type RM Length L Ch R = 1 ,23800   ,639,639,639
BEGIN DESCRIPTION:
Goat Creek 40.1
END DESCRIPTION:
XS GIS Cut Line= 3
      1906227.24     13952313.55       1905355.3     13952610.95
      1904157.78     13952816.57
#Sta/Elev= 30
  4280.6 1834.32  4294.9 1829.19  4456.5 1797.79  4488.5 1794.45  4538.9 1795.23
  4602.3 1788.34  4709.6    1784  4903.5 1773.21  4935.2  1765.4  4953.1  1752.1
  4961.5 1749.08  4985.9 1740.23  5009.2 1738.33  5009.7 1737.83  5032.2 1738.33
  5046.1  1741.7  5118.3 1746.13  5144.4  1750.4  5525.3 1755.47  5575.9 1755.77
  5676.5 1755.87    5725 1753.46  5885.9 1756.92  6043.4 1760.14  6078.8 1760.84
  6225.7 1765.88  6266.8 1769.17  6302.8 1775.83  6333.8 1780.49  6416.9 1783.99
#Mann= 12 ,-1 , 0
  4280.6     .07       0  4709.6      .1       0  4961.5    .035       0
  5009.2    .035       0  5032.2    .035       0  5525.3     .07       0
  5575.9    .063       0  5676.5    .035       0  5885.9     .07       0
  6043.4    .035       0  6078.8     .07       0  6302.8      .1       0
#Block Obstruct= 2 , 0
                         5595.61         1755.37
Bank Sta=5009.2,5032.2
XS Rating Curve= 0 ,0
Exp/Cntr=0.3,0.1

Type RM Length L Ch R = 1 ,23161   ,482,482,482
BEGIN DESCRIPTION:
Goat Creek 40.0
END DESCRIPTION:
XS GIS Cut Line= 3
      1905874.96     13951675.02      1905055.78     13952165.55
      1904119.75     13952792.12
#Sta/Elev= 30
  4052.7  1918.7  4094.9  1910.3    4250 1865.08  4336.2 1846.42  4469.1 1824.18
  4643.9 1804.23  4740.1 1785.86  4835.9 1778.28  4852.8 1777.07    4924 1774.03
  4953.1 1755.78    4991 1737.42  4991.5 1736.92    5014 1737.42  5041.1 1738.32
  5115.9 1744.32  5201.4 1747.23  5314.9 1750.99  5370.2 1751.18  5495.6 1748.55
  5580.8 1750.67  5651.3 1751.68  5682.7 1757.16    5816 1761.88  5817.2  1761.9
  5949.8  1764.8  5998.2 1770.32  6025.6 1775.67    6132 1784.63  6133.9 1784.67
#Mann= 16 ,-1 , 0
  4052.7      .1       0    4250     .07       0  4835.9      .1       0
  4852.8     .07       0  4953.1    .035       0    4991    .035       0
    5014    .035       0  5041.1     .07       0  5201.4    .035       0
  5314.9     .07       0  5370.2    .035       0  5580.8     .07       0
    5816    .035       0  5817.2     .07       0  5998.2      .1       0
    6132     .07       0
#Block Obstruct= 2 , 0
                         5356.59         1750.49
Bank Sta=4991,5014
XS Rating Curve= 0 ,0
Exp/Cntr=0.3,0.1

Type RM Length L Ch R = 1 ,22679   ,568,568,568
BEGIN DESCRIPTION:
Goat Creek 39.0
END DESCRIPTION:
XS GIS Cut Line= 3
      1905424.98     13951475.01        1904625.       13952025.
      1904074.97     13952775.03
#Sta/Elev= 30
  4029.2 1854.76  4158.3 1816.99  4203.3 1809.45    4237 1796.25  4272.2 1787.32
    4328 1780.08    4403 1774.75  4491.7 1771.32  4493.4 1771.26  4661.4 1767.68
  4848.5 1762.04    4896 1756.13  4941.7 1737.79  4997.6 1735.96  5001.7 1733.36
  5002.2 1732.86  5024.8 1733.36    5043 1739.66  5123.2 1742.42  5255.8 1742.18
  5288.5 1746.24  5362.4 1743.45  5401.3 1753.21  5428.5 1755.27  5544.1 1758.95
  5718.4 1762.15    5793 1768.97  5827.9 1776.16  5889.5 1782.82  5930.1  1785.6
#Mann= 15 ,-1 , 0
  4029.2     .07       0  4158.3      .1       0    4403     .07       0
  4491.7      .1       0  4493.4     .07       0  4661.4      .1       0
  4848.5     .07       0  5001.7     .05       0  5024.8     .07       0
  5123.2    .035       0  5428.5     .07       0  5544.1    .035       0
  5718.4     .07       0    5793      .1       0  5889.5     .07       0
#Block Obstruct= 2 , 0
                         5291.99         1745.77
Bank Sta=5001.7,5024.8
XS Rating Curve= 0 ,0
Exp/Cntr=0.3,0.1

Type RM Length L Ch R = 1 ,22111   ,209,209,209
BEGIN DESCRIPTION:
Goat Creek 38.0
END DESCRIPTION:
XS GIS Cut Line= 3
      1904574.96     13951725.01        1904175.       13951775.
      1903824.99     13951975.01
#Sta/Elev= 30
  4592.3 1761.85    4655 1761.33  4679.2 1759.89  4697.4 1756.96  4721.5 1750.69
  4736.7  1748.2  4854.4 1745.73  4884.8 1744.68  4890.8 1742.75  4893.9 1740.58
  4902.9 1736.95  4942.5 1738.48  4948.3 1737.11  4954.3  1733.9  4960.4 1732.08
  4993.6 1731.08  5000.7 1730.24  5002.5 1728.88    5003 1728.38  5025.8 1728.88
  5027.9 1729.96  5033.4 1730.43  5038.3 1731.83    5059 1748.19  5062.5 1749.25
    5104 1753.15  5152.1 1753.89  5193.8  1755.1  5277.9 1760.14  5398.5 1764.93
#Mann= 6 ,-1 , 0
  4592.3     .07       0  4854.4    .035       0  5002.5    .035       0
  5025.8    .035       0  5152.1     .07       0  5277.9    .035       0
Bank Sta=5002.5,5025.8
XS Rating Curve= 0 ,0
Exp/Cntr=0.3,0.1

Type RM Length L Ch R = 1 ,21902   ,324,324,324
BEGIN DESCRIPTION:
Mapping XS d3556d17
END DESCRIPTION:
XS GIS Cut Line= 2
      1904559.61     13951582.64      1903779.14     13951626.45
#Sta/Elev= 30
  4531.6 1760.46  4599.6 1759.91  4651.4 1758.02  4677.7 1755.58  4710.8 1748.55
    4741 1746.43  4804.2 1744.68    4825 1741.19    4864 1742.54    4879 1739.39
  4903.1 1736.98  4921.1 1733.09  4951.1 1731.69  4954.2 1731.34  4954.5 1730.24
    4955 1729.74  4977.9 1730.24  4999.2 1730.71  5002.2  1733.2  5005.2 1737.56
  5011.1 1740.38  5017.5 1744.87  5026.3 1747.99  5042.9 1750.78  5062.2 1751.84
  5110.4 1754.85  5128.4 1753.72  5152.1 1756.24  5209.6 1758.53  5313.3  1760.8
#Mann= 6 ,-1 , 0
  4531.6     .07       0    4741    .035       0  4954.5     .05       0
  4977.9    .035       0  5062.2    .035       0  5152.1     .07       0
Bank Sta=4954.5,4977.9
XS Rating Curve= 0 ,0
Exp/Cntr=0.3,0.1

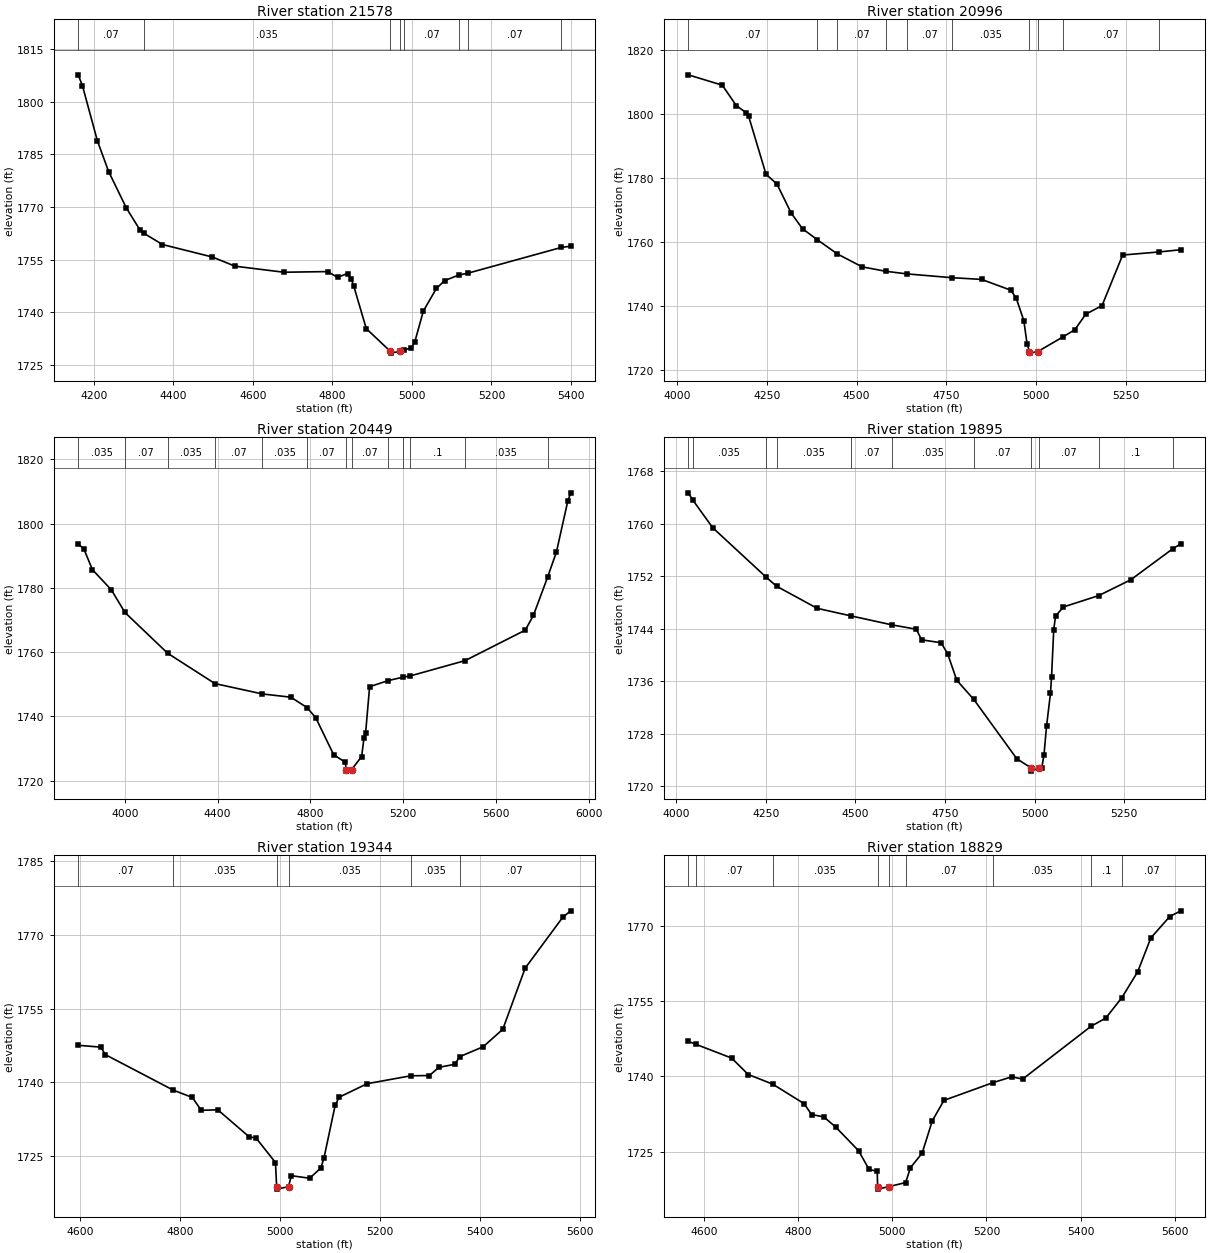
Type RM Length L Ch R = 1 ,21578   ,582,582,582
BEGIN DESCRIPTION:
Goat Creek 37.0
END DESCRIPTION:
XS GIS Cut Line= 3
      1904924.96     13951075.01        1904125.       13951325.
      1903725.01       13951325.
#Sta/Elev= 30
  4161.1 1807.71  4171.8 1804.63  4209.5 1788.86  4237.8  1780.1  4281.8 1769.83
  4316.4 1763.47    4326 1762.55    4373 1759.32  4498.7 1755.75  4555.3 1753.14
  4677.9 1751.42  4787.9  1751.6    4813 1749.98  4838.2 1751.03  4847.6 1749.53
  4853.9 1747.45  4885.3 1735.33  4945.9 1728.85  4946.4 1728.35  4969.4 1728.85
  4980.6 1729.25  4998.5 1729.89  5007.5 1731.66  5028.8 1740.35  5061.5 1746.79
  5082.5 1749.04  5117.9 1750.62  5141.3 1751.16    5376  1758.5  5399.2 1758.84
#Mann= 8 ,-1 , 0
  4161.1     .07       0    4326    .035       0  4945.9     .05       0
  4969.4    .035       0  4980.6     .07       0  5117.9    .035       0
  5141.3     .07       0    5376      .1       0
Bank Sta=4945.9,4969.4
XS Rating Curve= 0 ,0
Exp/Cntr=0.3,0.1

Type RM Length L Ch R = 1 ,20996   ,547,547,547
BEGIN DESCRIPTION:
Goat Creek 36.0
END DESCRIPTION:
XS GIS Cut Line= 3
      1905080.28     13950938.68        1904125.       13950775.
      1903725.01       13950825.
#Sta/Elev= 30
  4030.8 1812.17  4125.7 1808.94  4164.7 1802.58  4192.7 1800.33  4198.8 1799.35
  4247.5 1781.17  4277.9 1778.14  4317.5 1769.09  4349.2 1764.17  4390.3 1760.78
  4446.5 1756.31  4515.3 1752.31  4580.7 1750.93    4640 1750.11  4765.5 1748.93
  4848.1 1748.39  4929.3 1745.04  4944.5 1742.58  4965.8 1735.54  4974.9 1728.23
  4981.4 1725.91  4981.9 1725.41  5004.9 1725.91  5074.6 1730.45  5108.1 1732.73
  5138.3 1737.54  5183.7 1740.23  5241.1 1755.99  5341.3 1756.94  5403.1 1757.64
#Mann= 10 ,-1 , 0
  4030.8     .07       0  4390.3    .035       0  4446.5     .07       0
  4580.7    .035       0    4640     .07       0  4765.5    .035       0
  4981.4    .035       0  5004.9    .035       0  5074.6     .07       0
  5341.3      .1       0
Bank Sta=4981.4,5004.9
XS Rating Curve= 0 ,0
Exp/Cntr=0.3,0.1

Type RM Length L Ch R = 1 ,20449   ,554,554,554
BEGIN DESCRIPTION:
Goat Creek 35.0
END DESCRIPTION:
XS GIS Cut Line= 3
      1905129.49     13950622.46        1903975.       13950275.
      1903175.02     13950724.99
#Sta/Elev= 30
  3798.6  1793.6  3822.4 1792.24    3860 1785.67  3941.4  1779.4  4000.2 1772.35
  4184.2 1759.66  4388.2 1750.21  4592.1 1746.99  4715.3 1745.97  4785.7 1742.73
  4823.3 1739.52  4900.1 1728.06  4950.2 1725.73  4954.1 1723.46  4954.6 1722.96
  4977.7 1723.46  5020.6 1727.49    5031 1733.35  5037.8 1734.84  5055.1 1749.24
  5134.4 1751.12  5198.4  1752.2  5229.9 1752.58  5466.5 1757.35  5726.2 1766.84
  5761.3 1771.45  5822.4 1783.32  5860.5 1791.17  5909.2 1806.93  5922.1 1809.58
#Mann= 13 ,-1 , 0
  3798.6    .035       0  4000.2     .07       0  4184.2    .035       0
  4388.2     .07       0  4592.1    .035       0  4785.7     .07       0
  4954.1     .05       0  4977.7     .07       0  5134.4      .1       0
  5198.4     .07       0  5229.9      .1       0  5466.5    .035       0
  5822.4     .07       0
Bank Sta=4954.1,4977.7
XS Rating Curve= 0 ,0
Exp/Cntr=0.3,0.1

Type RM Length L Ch R = 1 ,19895   ,551,551,551
BEGIN DESCRIPTION:
Goat Creek 34.0
END DESCRIPTION:
XS GIS Cut Line= 3
      1904874.99     13950324.99        1904075.       13949775.
      1903675.03       13949825.
#Sta/Elev= 30
  4033.6 1764.67  4045.7 1763.62  4101.9 1759.36  4250.9 1751.84  4279.8 1750.47
  4393.1  1747.1  4486.4 1745.96  4602.6 1744.57  4669.8 1743.92  4684.4 1742.31
    4739 1741.86  4757.2 1740.18  4782.7 1736.15  4830.2 1733.23  4950.1 1724.21
  4989.7 1722.83  4990.2 1722.33  5013.3 1722.83  5019.8 1722.88  5025.9 1724.79
    5033 1729.15    5044 1734.16    5047 1736.66  5053.1 1743.85  5058.1 1745.92
  5080.3 1747.31  5178.3 1749.03  5267.7 1751.43  5384.6 1756.14  5407.5 1756.92
#Mann= 11 ,-1 , 0
  4033.6     .07       0  4045.7    .035       0  4250.9     .07       0
  4279.8    .035       0  4486.4     .07       0  4602.6    .035       0
  4830.2     .07       0  4989.7     .05       0  5013.3     .07       0
  5178.3      .1       0  5384.6    .035       0
Bank Sta=4989.7,5013.3
XS Rating Curve= 0 ,0
Exp/Cntr=0.3,0.1

Type RM Length L Ch R = 1 ,19344   ,515,515,515
BEGIN DESCRIPTION:
Goat Creek 33.0
END DESCRIPTION:
XS GIS Cut Line= 3
      1904675.05       13949325.        1904275.       13949325.
      1903724.99     13949124.99
#Sta/Elev= 30
  4596.1 1747.52  4641.4 1747.15  4650.4 1745.63  4785.9 1738.42  4824.4 1736.91
  4842.4 1734.29  4875.4  1734.4  4938.4 1728.88  4951.8 1728.68  4990.8 1723.67
  4993.1 1718.76  4993.6 1718.26  5016.9 1718.76  5022.4    1721  5059.2 1720.47
  5081.6 1722.57    5088 1724.69  5110.3 1735.37  5118.4 1736.97  5174.1 1739.71
  5261.5 1741.32  5298.6 1741.37  5317.8 1743.04  5349.7 1743.66  5359.2  1745.2
  5406.3 1747.23  5445.5 1750.78  5490.2 1763.21  5565.5 1773.57  5581.4 1774.88
#Mann= 6 ,-1 , 0
  4596.1     .07       0  4785.9    .035       0  4993.1    .035       0
  5016.9    .035       0  5261.5    .035       0  5359.2     .07       0
Bank Sta=4993.1,5016.9
XS Rating Curve= 0 ,0
Exp/Cntr=0.3,0.1

Type RM Length L Ch R = 1 ,18829   ,532,532,532
BEGIN DESCRIPTION:
Goat Creek 32.0
END DESCRIPTION:
XS GIS Cut Line= 3
      1904724.98     13949024.99        1904325.       13948875.
      1903725.04     13949024.99
#Sta/Elev= 30
  4567.1 1746.98  4583.6 1746.39  4659.2 1743.66  4694.5 1740.39  4746.4 1738.48
    4813  1734.6    4829 1732.43  4854.7 1731.97  4880.3 1729.93  4928.7 1725.24
  4950.8 1721.54  4968.3 1721.12  4969.1  1718.1  4969.6  1717.6  4992.9  1718.1
  5028.6  1718.9  5038.9 1721.87  5063.6 1724.75  5085.3 1731.21    5110 1735.25
  5213.3 1738.75    5254 1739.94    5277 1739.48  5422.4    1750  5453.3  1751.6
  5487.6 1755.67  5521.3 1760.84  5549.1 1767.55  5589.3 1771.81  5612.7 1772.94
#Mann= 9 ,-1 , 0
  4567.1    .035       0  4583.6     .07       0  4746.4    .035       0
  4969.1    .035       0  4992.9    .035       0  5028.6     .07       0
  5213.3    .035       0  5422.4      .1       0  5487.6     .07       0
Bank Sta=4969.1,4992.9
XS Rating Curve= 0 ,0
Exp/Cntr=0.3,0.1

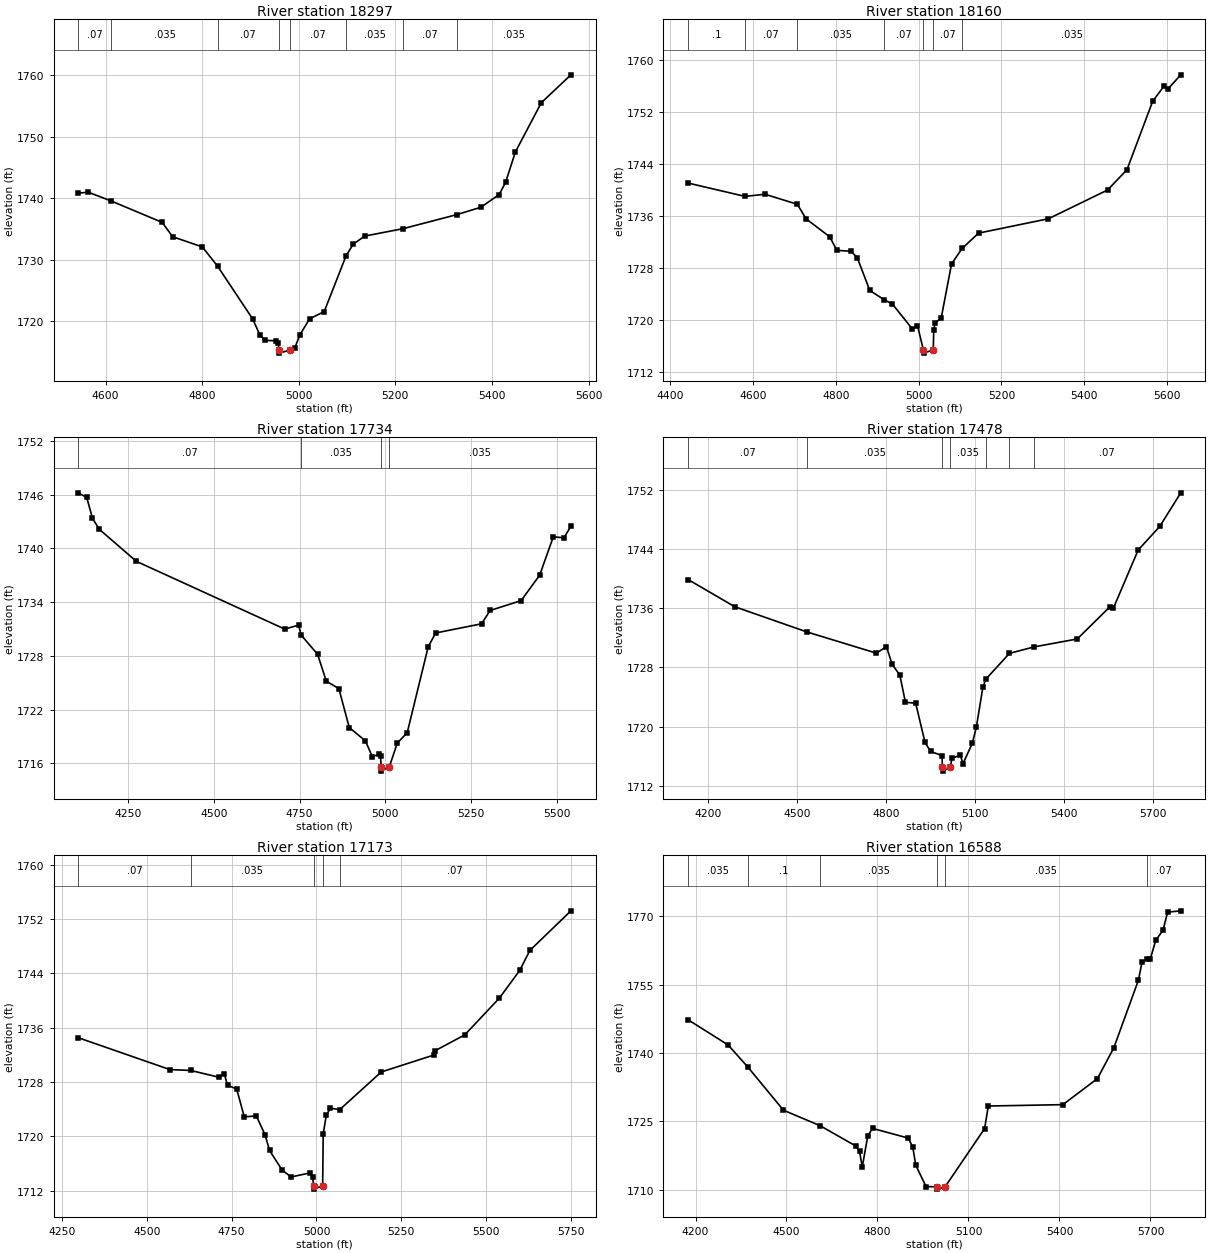
Type RM Length L Ch R = 1 ,18297   ,137,137,137
BEGIN DESCRIPTION:
Goat Creek 31.0
END DESCRIPTION:
XS GIS Cut Line= 3
      1904674.97     13948674.98        1904325.       13948375.
      1903824.96     13948625.02
#Sta/Elev= 30
  4543.4 1740.84  4564.4 1740.99  4612.3 1739.55  4717.5 1736.08  4738.8 1733.76
  4800.5  1732.1  4832.4 1728.92  4904.8 1720.36  4919.7 1717.75    4931  1716.9
  4952.6 1716.84    4958 1716.48  4958.5 1715.33    4959 1714.83  4982.4 1715.33
    4992  1715.7  5002.1 1717.77  5022.5 1720.41  5052.7 1721.58  5098.1 1730.68
  5113.1 1732.57  5136.6 1733.86  5216.2 1735.07  5328.2 1737.37    5377 1738.55
    5415 1740.62  5428.4 1742.65  5448.5 1747.55  5502.1 1755.54  5563.4 1760.08
#Mann= 8 ,-1 , 0
  4543.4     .07       0  4612.3    .035       0  4832.4     .07       0
  4958.5     .05       0  4982.4     .07       0  5098.1    .035       0
  5216.2     .07       0  5328.2    .035       0
Bank Sta=4958.5,4982.4
XS Rating Curve= 0 ,0
Exp/Cntr=0.3,0.1

Type RM Length L Ch R = 1 ,18160   ,426,426,426
BEGIN DESCRIPTION:
Goat Creek 30.1
END DESCRIPTION:
XS GIS Cut Line= 5
      1904856.07     13948489.36      1904527.91      13948283.6
      1904376.87     13948262.77      1904236.24     13948244.54
      1903793.56     13948494.53
#Sta/Elev= 30
  4443.1 1741.03  4580.7 1738.98  4628.8 1739.31  4707.1 1737.77    4728 1735.54
  4785.6 1732.76  4802.3 1730.69  4836.7 1730.56  4851.8 1729.56  4882.1 1724.53
  4916.9 1723.11  4936.6 1722.45  4985.1  1718.6  4997.2 1719.15  5011.4 1715.41
  5011.9 1714.91  5035.3 1715.41  5036.5 1718.42  5039.5  1719.5  5054.6 1720.33
  5079.5 1728.61  5105.1    1731  5144.8 1733.34  5313.6 1735.55  5456.2 1739.96
  5503.1 1743.07  5565.2 1753.59  5592.7 1755.92  5603.1 1755.55  5633.1 1757.65
#Mann= 7 ,-1 , 0
  4443.1      .1       0  4580.7     .07       0  4707.1    .035       0
  4916.9     .07       0  5011.4     .05       0  5035.3     .07       0
  5105.1    .035       0
Bank Sta=5011.4,5035.3
XS Rating Curve= 0 ,0
Exp/Cntr=0.3,0.1

Type RM Length L Ch R = 1 ,17734   ,256,256,256
BEGIN DESCRIPTION:
Goat Creek 30.0
END DESCRIPTION:
XS GIS Cut Line= 3
      1905224.98     13948274.99        1904425.       13947875.
      1903975.03     13948174.98
#Sta/Elev= 30
  4105.2  1746.2  4130.1 1745.69  4146.9 1743.35    4167 1742.12  4274.8 1738.55
    4707 1730.99  4747.2 1731.44  4754.7 1730.32  4802.7 1728.17  4827.7 1725.19
  4864.6 1724.34  4894.8    1720  4941.8 1718.52  4961.9 1716.76    4982 1717.02
  4985.9  1716.8  4987.7 1715.64  4988.2 1715.14  5011.6 1715.64  5034.8 1718.28
  5063.6 1719.43  5124.9 1729.04  5146.6 1730.56    5280 1731.58  5305.2 1733.07
  5395.4 1734.17  5449.4 1737.01  5489.1 1741.29  5520.2 1741.18  5540.4 1742.48
#Mann= 4 ,-1 , 0
  4105.2     .07       0  4754.7    .035       0  4987.7    .035       0
  5011.6    .035       0
Bank Sta=4987.7,5011.6
XS Rating Curve= 0 ,0
Exp/Cntr=0.3,0.1

Type RM Length L Ch R = 1 ,17478   ,305,305,305
BEGIN DESCRIPTION:
Goat Creek 29.1
END DESCRIPTION:
XS GIS Cut Line= 4
      1905148.58     13948154.32      1904662.44     13947692.49
      1904374.24     13947605.68      1903704.15      13947442.5
#Sta/Elev= 30
  4132.3 1739.89  4289.7 1736.21    4533  1732.8  4767.2 1729.93  4801.1 1730.82
  4820.1 1728.46  4846.4 1726.95  4865.2 1723.28  4899.7 1723.17    4931 1717.89
  4949.8 1716.65  4988.7 1716.08  4989.7 1714.48  4990.2 1713.98  5016.5 1714.48
  5021.9 1715.74  5050.1 1716.11  5059.5 1715.01  5090.8 1717.75  5104.3 1719.94
  5126.6 1725.39  5137.1 1726.45  5215.8  1729.9  5298.1 1730.77  5444.4 1731.85
  5554.1 1736.18  5566.5 1736.03  5649.9 1743.88  5722.5 1747.06  5793.5 1751.61
#Mann= 7 ,-1 , 0
  4132.3     .07       0    4533    .035       0  4989.7    .035       0
  5016.5    .035       0  5137.1     .07       0  5215.8    .035       0
  5298.1     .07       0
Bank Sta=4989.7,5016.5
XS Rating Curve= 0 ,0
Exp/Cntr=0.3,0.1

Type RM Length L Ch R = 1 ,17173   ,585,585,585
BEGIN DESCRIPTION:
Goat Creek 29.0
END DESCRIPTION:
XS GIS Cut Line= 3
      1905054.89     13947684.31        1904425.       13947375.
      1903674.85     13947369.49
#Sta/Elev= 30
  4297.8 1734.52  4567.6 1729.83  4629.7 1729.69  4713.1 1728.69    4728 1729.24
    4738  1727.5  4764.8 1726.98  4787.1 1722.87  4822.9 1722.99  4848.3 1720.23
  4861.7 1717.92  4898.5 1715.04  4925.2 1714.01    4982 1714.62  4988.7 1714.04
  4991.4 1712.72  4991.9 1712.22  5018.2 1712.72  5019.8 1720.36  5028.8 1723.07
  5040.8 1724.15  5068.2 1723.91  5190.8 1729.47  5346.8 1731.98  5349.8 1732.61
  5436.8 1734.93  5538.8 1740.34  5598.8 1744.42  5628.8 1747.37  5749.7  1753.2
#Mann= 5 ,-1 , 0
  4297.8     .07       0  4629.7    .035       0  4991.4    .035       0
  5018.2    .035       0  5068.2     .07       0
Bank Sta=4991.4,5018.2
XS Rating Curve= 0 ,0
Exp/Cntr=0.3,0.1

Type RM Length L Ch R = 1 ,16588   ,636,636,636
BEGIN DESCRIPTION:
Goat Creek 28.0
END DESCRIPTION:
XS GIS Cut Line= 3
      1905324.99       13947025.        1904525.       13946825.
      1903725.01       13946825.
#Sta/Elev= 30
  4175.4 1747.32  4307.8 1741.76  4372.2 1736.95  4490.1 1727.44  4611.2 1724.04
  4728.2  1719.6  4740.8 1718.43  4749.8 1714.98    4768 1721.83  4783.8 1723.45
  4901.3 1721.33  4916.4 1719.35  4926.3 1715.34  4960.1 1710.69  4995.8 1710.62
  4996.3 1710.12  5022.8 1710.62  5153.3 1723.42  5165.3 1728.37  5411.3 1728.67
  5525.3  1734.4  5579.3 1741.17  5660.3 1755.99  5672.3 1759.99  5687.3 1760.59
  5699.3  1760.6  5717.6 1764.78  5741.3 1766.94  5756.6 1770.94    5800 1771.23
#Mann= 6 ,-1 , 0
  4175.4    .035       0  4372.2      .1       0  4611.2    .035       0
  4995.8    .035       0  5022.8    .035       0  5687.3     .07       0
#Block Obstruct= 2 , 0
         4779.07 1722.65
Bank Sta=4995.8,5022.8
XS Rating Curve= 0 ,0
Exp/Cntr=0.3,0.1

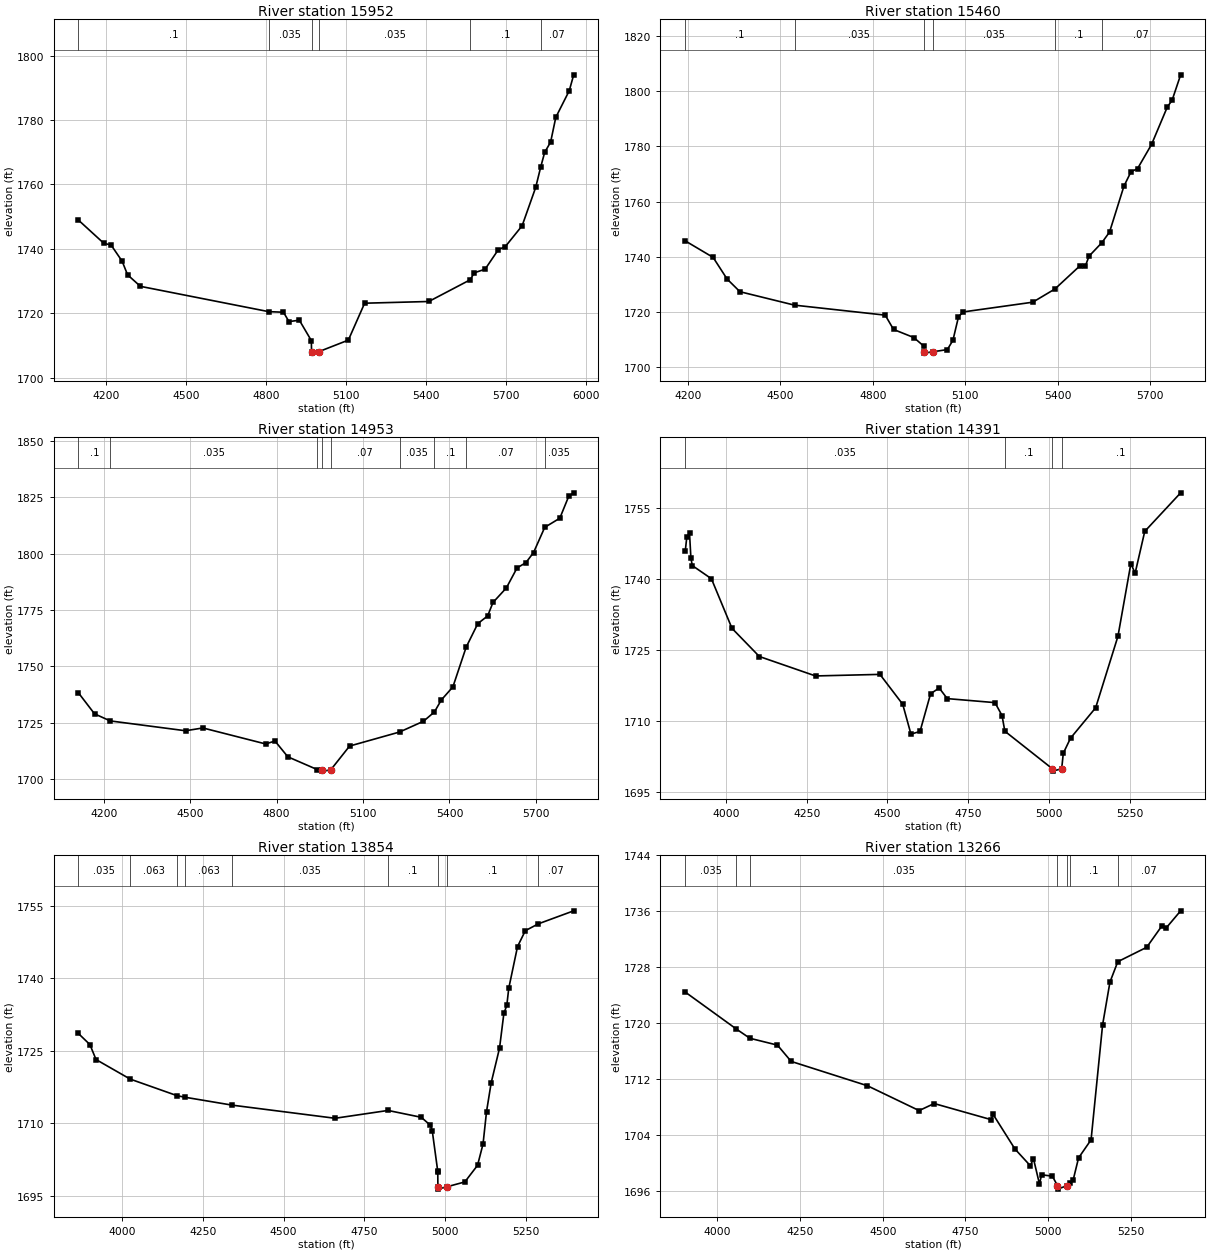
Type RM Length L Ch R = 1 ,15952   ,492,492,492
BEGIN DESCRIPTION:
Goat Creek 27.0
END DESCRIPTION:
XS GIS Cut Line= 4
        1905325.       13945825.      1904614.98     13946224.39
      1904451.52     13946224.48      1903724.97     13945724.98
#Sta/Elev= 30
  4095.3 1748.97  4190.9 1741.75  4218.4 1741.19  4259.7  1736.2  4280.3 1731.95
  4328.5 1728.38    4810 1720.53  4865.5 1720.35  4886.1 1717.45  4925.2 1717.87
  4970.2 1711.54  4970.9 1708.16  4971.4 1707.66  4999.6 1708.16  5109.1  1711.7
  5170.2 1723.15  5411.1 1723.68  5566.9 1730.43  5581.6 1732.58  5622.5  1733.7
  5672.6 1739.81  5698.1 1740.69  5761.5 1747.18  5812.4 1759.07  5831.4 1765.44
  5846.2 1769.97  5868.5 1773.15  5887.9 1780.81  5938.4 1789.08  5955.1 1794.01
#Mann= 6 ,-1 , 0
  4095.3      .1       0    4810    .035       0  4970.9    .035       0
  4999.6    .035       0  5566.9      .1       0  5831.4     .07       0
Bank Sta=4970.9,4999.6
XS Rating Curve= 0 ,0
Exp/Cntr=0.3,0.1

Type RM Length L Ch R = 1 ,15460   ,507,507,507
BEGIN DESCRIPTION:
Goat Creek 26.0
END DESCRIPTION:
XS GIS Cut Line= 3
      1905274.98       13945775.        1904475.       13945775.
      1903675.01       13945675.
#Sta/Elev= 30
    4192 1745.78  4282.3  1739.8  4327.6 1731.97  4369.3 1727.37  4546.2  1722.5
  4840.3 1718.88  4867.3  1713.7  4932.9 1710.77  4966.3 1707.57  4966.9 1705.62
  4967.4 1705.12  4995.6 1705.62  5041.6  1706.4  5059.8 1709.74  5077.9 1718.28
    5093 1720.04  5318.6 1723.57  5390.5 1728.35    5471 1736.68  5489.1 1736.63
  5501.2 1740.25  5542.9 1745.15  5567.7 1748.99  5614.2 1765.57  5637.2 1770.82
  5658.4 1771.95  5703.8 1780.71  5755.2 1794.35  5770.3 1796.66  5798.2 1805.94
#Mann= 6 ,-1 , 0
    4192      .1       0  4546.2    .035       0  4966.9    .035       0
  4995.6    .035       0  5390.5      .1       0  5542.9     .07       0
Bank Sta=4966.9,4995.6
XS Rating Curve= 0 ,0
Exp/Cntr=0.3,0.1

Type RM Length L Ch R = 1 ,14953   ,562,562,562
BEGIN DESCRIPTION:
Goat Creek 25.0
END DESCRIPTION:
XS GIS Cut Line= 3
      1905175.04     13945725.02        1904375.       13945325.
        1903575.       13945525.
#Sta/Elev= 30
    4112 1738.33  4168.3 1728.94  4222.9  1725.8    4484 1721.44  4544.4 1722.68
  4761.9 1715.59  4794.5 1716.88  4839.1 1709.88    4942 1704.17  4958.8 1704.03
  4959.3 1703.53  4987.6 1704.03  5053.4 1714.65  5226.8 1720.88  5309.8 1725.65
  5347.8 1729.78  5371.7 1735.09  5411.9  1740.9  5457.9 1758.51  5498.4 1768.98
  5532.5 1772.37    5551 1778.34  5597.4 1784.79  5634.5 1793.66  5665.4 1796.03
  5691.8 1800.49  5730.6 1811.67  5782.9 1815.72  5813.9 1825.45  5831.1 1826.98
#Mann= 9 ,-1 , 0
    4112      .1       0  4222.9    .035       0    4942     .07       0
  4958.8     .05       0  4987.6     .07       0  5226.8    .035       0
  5347.8      .1       0  5457.9     .07       0  5730.6    .035       0
Bank Sta=4958.8,4987.6
XS Rating Curve= 0 ,0
Exp/Cntr=0.3,0.1

Type RM Length L Ch R = 1 ,14391   ,537,537,537
BEGIN DESCRIPTION:
Goat Creek 24.0
END DESCRIPTION:
XS GIS Cut Line= 3
      1905275.03     13945625.03        1904475.       13944825.
      1904125.02     13944625.01
#Sta/Elev= 30
  3873.6 1745.82  3878.3 1748.76  3886.8 1749.58    3891 1744.45  3895.2 1742.77
  3954.6 1739.98  4018.3  1729.5  4103.1 1723.54  4277.1 1719.43  4476.6 1719.76
  4547.2 1713.44  4572.7 1707.13  4600.8  1707.7  4633.6 1715.68  4660.2 1716.88
  4685.1 1714.64    4833 1713.79  4854.8 1711.06  4863.5 1707.75  5010.8 1699.81
  5011.3 1699.31  5039.6 1699.81  5044.6 1703.09    5067 1706.28  5144.8  1712.7
  5213.9 1727.82  5253.9 1743.18  5267.1 1741.15  5296.9 1749.99  5408.1 1758.14
#Mann= 4 ,-1 , 0
  3873.6    .035       0  4863.5      .1       0  5010.8     .05       0
  5039.6      .1       0
Bank Sta=5010.8,5039.6
XS Rating Curve= 0 ,0
Exp/Cntr=0.3,0.1

Type RM Length L Ch R = 1 ,13854   ,588,588,588
BEGIN DESCRIPTION:
Goat Creek 23.0
END DESCRIPTION:
XS GIS Cut Line= 3
      1905524.99     13945174.99        1904725.       13944375.
      1904324.97       13944325.
#Sta/Elev= 30
  3864.1 1728.61    3900  1726.3    3919  1723.2  4024.8 1719.15  4170.4 1715.71
  4194.2  1715.4  4341.4 1713.75  4659.4 1711.04  4823.6 1712.66  4926.5 1711.24
  4954.2 1709.62  4960.4 1708.49  4977.4 1700.11  4977.6 1699.97  4977.9 1696.87
  4978.4 1696.37  5006.7 1696.87  5061.4 1697.86  5100.7 1701.29  5117.8 1705.72
  5128.6 1712.42    5143 1718.39  5168.9 1725.57  5182.3 1732.75  5191.4  1734.4
  5197.4 1737.94  5224.6 1746.59  5248.8 1749.88  5289.2  1751.3  5398.6 1753.99
#Mann= 9 ,-1 , 0
  3864.1    .035       0  4024.8    .063       0  4170.4    .035       0
  4194.2    .063       0  4341.4    .035       0  4823.6      .1       0
  4977.9     .05       0  5006.7      .1       0  5289.2     .07       0
Bank Sta=4977.9,5006.7
XS Rating Curve= 0 ,0
Exp/Cntr=0.3,0.1

Type RM Length L Ch R = 1 ,13266   ,150,150,150
BEGIN DESCRIPTION:
Goat Creek 22.0
END DESCRIPTION:
XS GIS Cut Line= 3
      1905925.01     13944725.01        1905125.       13943975.
      1904725.01       13943975.
#Sta/Elev= 30
  3903.4 1724.41  4058.1 1719.11  4098.6  1717.8  4181.9 1716.82  4223.3 1714.49
  4453.5 1711.01  4609.9 1707.45  4655.3 1708.46  4827.1 1706.16  4833.5  1706.9
  4899.3 1701.96    4946 1699.55  4955.3 1700.58  4973.5 1696.94  4979.8 1698.26
  5012.4 1698.07  5027.9 1696.71  5028.4 1696.21  5056.8 1696.71  5066.3 1697.13
  5075.4 1697.54  5091.6 1700.68  5129.4 1703.27  5164.2 1719.72  5186.4 1725.84
  5210.1 1728.76  5297.4 1730.82  5342.4 1733.82  5355.6 1733.55    5400 1736.04
#Mann= 7 ,-1 , 0
  3903.4    .035       0  4058.1    .063       0  4098.6    .035       0
  5027.9    .035       0  5056.8    .035       0  5066.3      .1       0
  5210.1     .07       0
Bank Sta=5027.9,5056.8
XS Rating Curve= 0 ,0
Exp/Cntr=0.3,0.1

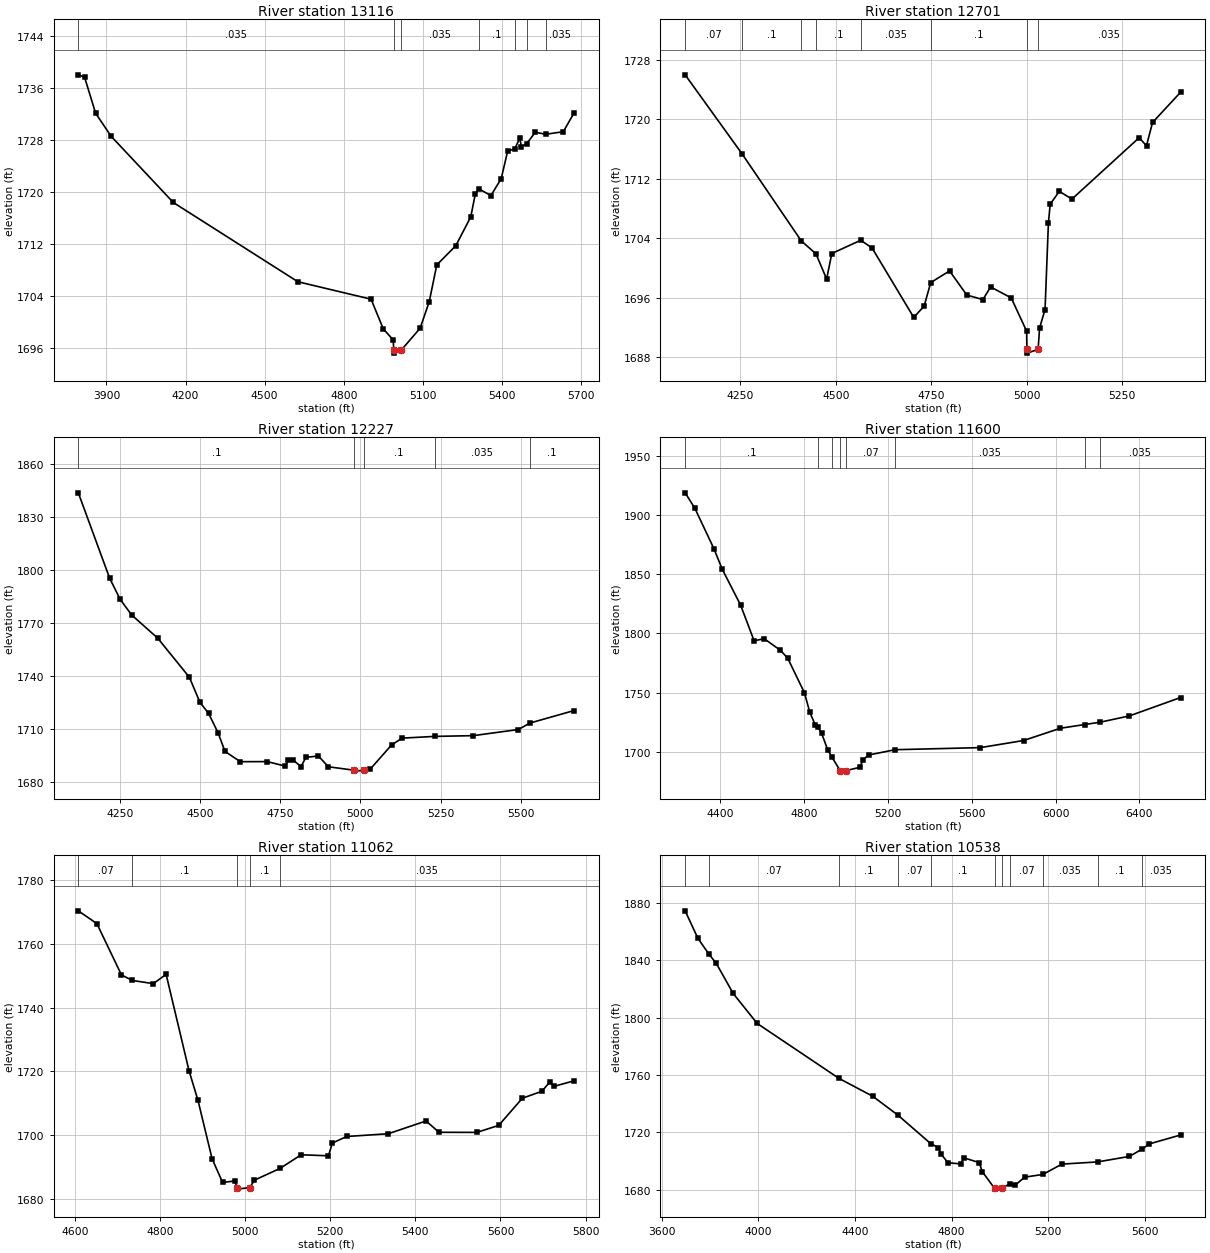
Type RM Length L Ch R = 1 ,13116   ,415,415,415
BEGIN DESCRIPTION:
Mapping XS eff96699
END DESCRIPTION:
XS GIS Cut Line= 3
      1906167.58     13944683.54      1905223.13     13943881.45
      1904893.28     13943332.86
#Sta/Elev= 30
  3793.4 1737.98  3817.3  1737.6    3859 1732.08    3918 1728.54  4153.6 1718.38
  4626.1 1706.21  4903.7 1703.53  4950.1 1698.97  4987.9 1697.26  4989.6 1695.75
  4990.1 1695.25    5019 1695.75  5089.8 1699.08  5124.3 1703.14  5152.9 1708.79
    5225 1711.74  5281.8 1716.17  5299.3 1719.74    5312 1720.48  5358.3 1719.44
  5397.3 1722.04  5421.7 1726.26  5449.1 1726.64  5467.3 1728.24  5474.2 1726.97
  5493.7  1727.4  5526.7 1729.17  5566.1 1728.85  5632.8 1729.25  5672.6 1732.06
#Mann= 7 ,-1 , 0
  3793.4    .035       0  4989.6    .035       0    5019    .035       0
    5312      .1       0  5449.1    .035       0  5493.7      .1       0
  5566.1    .035       0
Bank Sta=4989.6,5019
XS Rating Curve= 0 ,0
Exp/Cntr=0.3,0.1

Type RM Length L Ch R = 1 ,12701   ,474,474,474
BEGIN DESCRIPTION:
Goat Creek 21.0
END DESCRIPTION:
XS GIS Cut Line= 3
      1906275.03     13943975.01        1905475.       13943575.
      1905124.98     13943374.99
#Sta/Elev= 30
  4105.5 1725.96    4255 1715.31  4409.4 1703.67  4448.1 1701.91    4476 1698.53
  4489.5 1701.96  4565.3 1703.74  4594.9 1702.71  4704.1 1693.38  4731.3 1694.89
  4748.6 1698.06    4798 1699.62  4843.1 1696.38  4885.2 1695.77  4905.4 1697.47
  4959.4    1696  4999.7 1691.54  5000.4 1689.08  5000.9 1688.58  5029.8 1689.08
  5033.8 1691.98    5048 1694.43  5056.8 1706.07  5061.5 1708.59  5085.4 1710.31
  5118.4 1709.27  5294.3 1717.51  5313.7 1716.44  5329.5 1719.56  5403.1 1723.63
#Mann= 8 ,-1 , 0
  4105.5     .07       0    4255      .1       0  4409.4    .035       0
  4448.1      .1       0  4565.3    .035       0  4748.6      .1       0
  5000.4     .05       0  5029.8    .035       0
Bank Sta=5000.4,5029.8
XS Rating Curve= 0 ,0
Exp/Cntr=0.3,0.1

Type RM Length L Ch R = 1 ,12227   ,627,627,627
BEGIN DESCRIPTION:
Goat Creek 20.0
END DESCRIPTION:
XS GIS Cut Line= 3
      1906725.03       13943425.      1905976.24     13943441.26
        1905225.       13943175.
#Sta/Elev= 30
  4119.9 1843.87  4217.3 1795.58  4250.3 1783.43  4286.4 1774.53  4367.4 1761.42
  4466.4  1739.2  4499.4 1724.95  4526.4 1718.68  4556.4 1707.49  4577.4 1697.11
  4625.4 1691.27  4709.5 1691.31  4765.7 1688.75  4775.5 1692.13  4790.5 1692.09
  4814.8 1688.51  4830.1 1693.72  4868.9  1694.5  4900.2 1688.38  4981.1 1686.41
  4981.6 1685.91  5010.5 1686.41  5030.8 1687.06  5097.8 1700.86  5130.6 1704.64
  5231.7 1705.62  5352.3 1706.05  5492.9 1709.52  5529.1  1713.2  5665.9 1720.25
#Mann= 5 ,-1 , 0
  4119.9      .1       0  4981.1     .05       0  5010.5      .1       0
  5231.7    .035       0  5529.1      .1       0
Bank Sta=4981.1,5010.5
XS Rating Curve= 0 ,0
Exp/Cntr=0.3,0.1

Type RM Length L Ch R = 1 ,11600   ,538,538,538
BEGIN DESCRIPTION:
Goat Creek 19.0
END DESCRIPTION:
XS GIS Cut Line= 3
      1906924.97     13943324.99        1906225.       13943025.
      1904625.02       13943075.
#Sta/Elev= 30
    4234 1918.89  4280.1  1905.9  4371.5 1871.51  4410.6 1854.37  4498.5  1823.9
  4562.7 1793.76  4610.6 1795.58  4688.1 1785.75  4722.6 1779.21  4802.6 1749.88
  4828.4 1733.24  4854.5  1722.6  4868.2 1720.58  4884.8 1715.41  4913.3  1701.8
  4934.4 1695.28  4972.8 1684.09  4973.3 1683.59  5002.5 1684.09    5067 1686.82
    5082 1693.25    5109 1697.23  5234.7  1701.7  5641.6 1703.47  5847.3 1709.47
  6023.1 1719.85  6138.6 1722.97  6212.7 1724.97  6351.6 1730.26  6596.3 1745.84
#Mann= 8 ,-1 , 0
    4234      .1       0  4868.2    .033       0  4934.4     .07       0
  4972.8     .05       0  5002.5     .07       0  5234.7    .035       0
  6138.6      .1       0  6212.7    .035       0
Bank Sta=4972.8,5002.5
XS Rating Curve= 0 ,0
Exp/Cntr=0.3,0.1

Type RM Length L Ch R = 1 ,11062   ,524,524,524
BEGIN DESCRIPTION:
Goat Creek 18.0
END DESCRIPTION:
XS GIS Cut Line= 3
      1906374.96       13942575.        1905975.       13942575.
      1905225.01       13942725.
#Sta/Elev= 30
  4607.6 1770.41  4651.2 1766.39    4709 1750.27  4734.8 1748.52    4784 1747.53
    4814 1750.45    4868 1720.09    4889 1710.81    4922 1692.52  4946.7 1685.06
  4975.2 1685.49  4981.3 1683.45  4981.8 1682.95    5011 1683.45  5021.2 1685.74
  5082.4  1689.5  5131.4 1693.75  5195.6 1693.42  5204.8 1697.42  5238.4 1699.49
  5336.3 1700.36  5425.1 1704.37  5455.6 1700.81  5544.4 1700.78  5595.8 1702.97
  5651.5 1711.52  5697.3 1713.69  5715.7 1716.56  5725.8 1715.25  5772.4 1716.96
#Mann= 5 ,-1 , 0
  4607.6     .07       0  4734.8      .1       0  4981.3     .05       0
    5011      .1       0  5082.4    .035       0
Bank Sta=4981.3,5011
XS Rating Curve= 0 ,0
Exp/Cntr=0.3,0.1

Type RM Length L Ch R = 1 ,10538   ,545,545,545
BEGIN DESCRIPTION:
Goat Creek 17.0
END DESCRIPTION:
XS GIS Cut Line= 4
      1907018.52     13942278.51      1906155.38     13942135.87
        1905725.       13942175.        1905175.       13942675.
#Sta/Elev= 30
  3697.6 1874.44  3750.2  1855.3  3796.9 1844.04  3826.2 1837.88  3896.2 1816.86
  3995.6 1795.92  4334.7 1757.55  4473.9 1745.15  4577.8 1732.01  4714.1 1712.09
  4745.9 1709.38    4755 1705.19  4785.1 1698.81  4837.4    1698  4851.4  1702.2
  4914.6 1698.91  4926.7 1692.69    4978 1680.91  4978.5 1680.41  5007.8 1680.91
  5041.7 1684.26  5061.9 1682.99  5102.4 1688.77  5177.6 1690.63  5256.5 1697.86
    5404 1699.37  5536.2 1703.23  5588.9 1708.36  5617.8 1711.91  5747.9 1718.18
#Mann= 11 ,-1 , 0
  3697.6      .1       0  3796.9     .07       0  4334.7      .1       0
  4577.8     .07       0  4714.1      .1       0    4978     .05       0
  5007.8      .1       0  5041.7     .07       0  5177.6    .035       0
    5404      .1       0  5588.9    .035       0
Bank Sta=4978,5007.8
XS Rating Curve= 0 ,0
Exp/Cntr=0.3,0.1