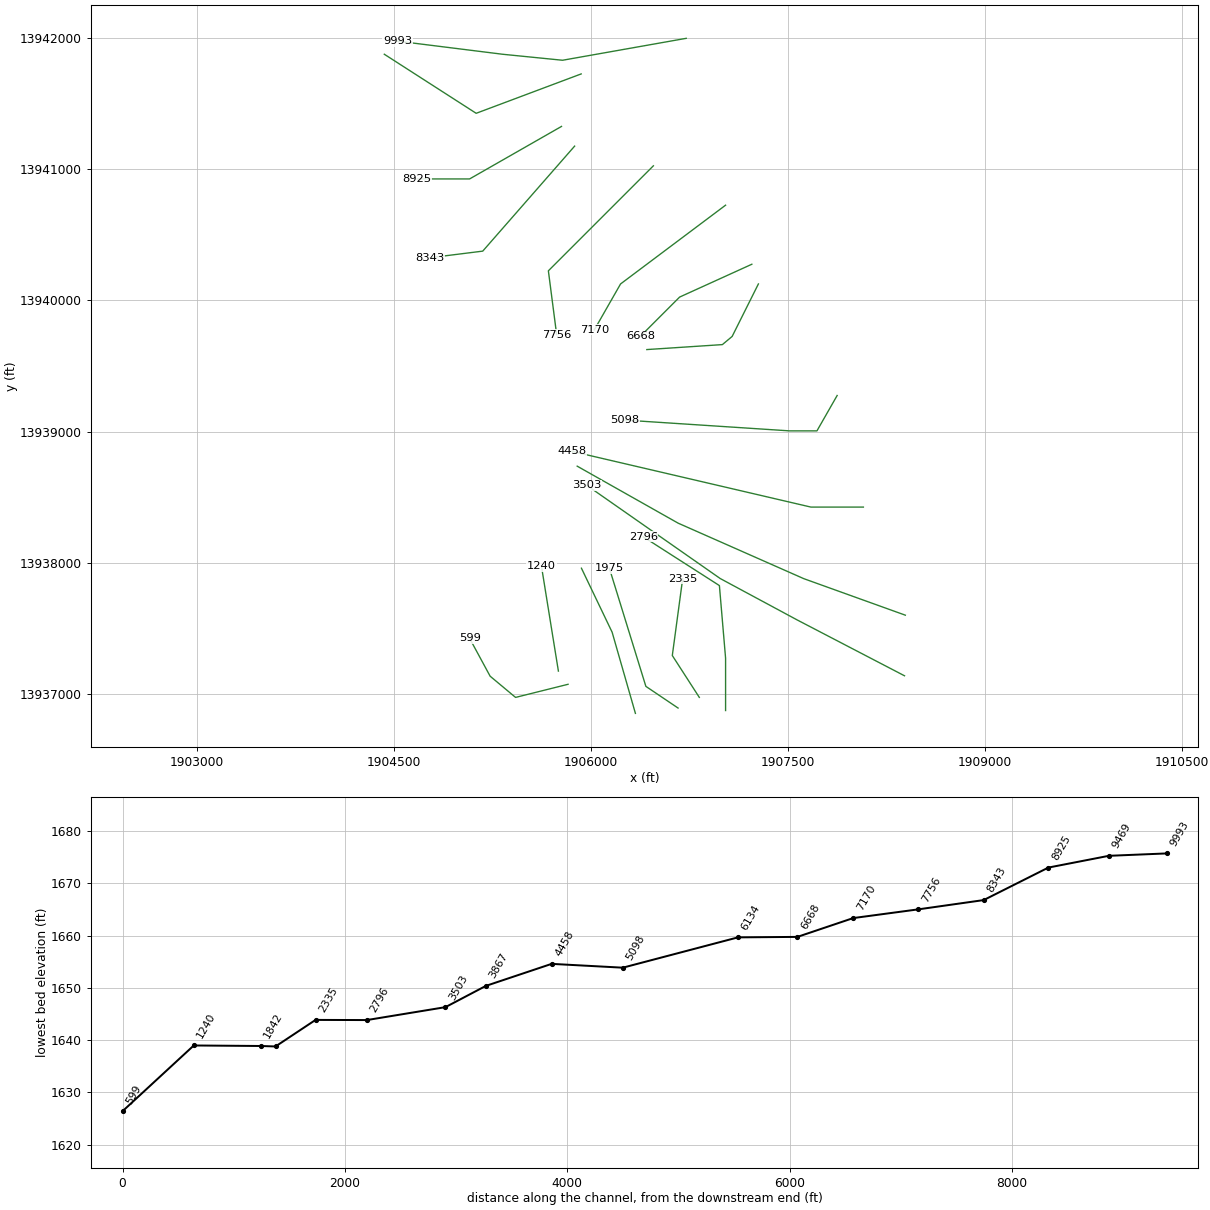
HEC-RAS study Goat Creek.prj: Goat Creek Base Level Engineering

--- Goat Creek.g01 (geometry) --- (continued)

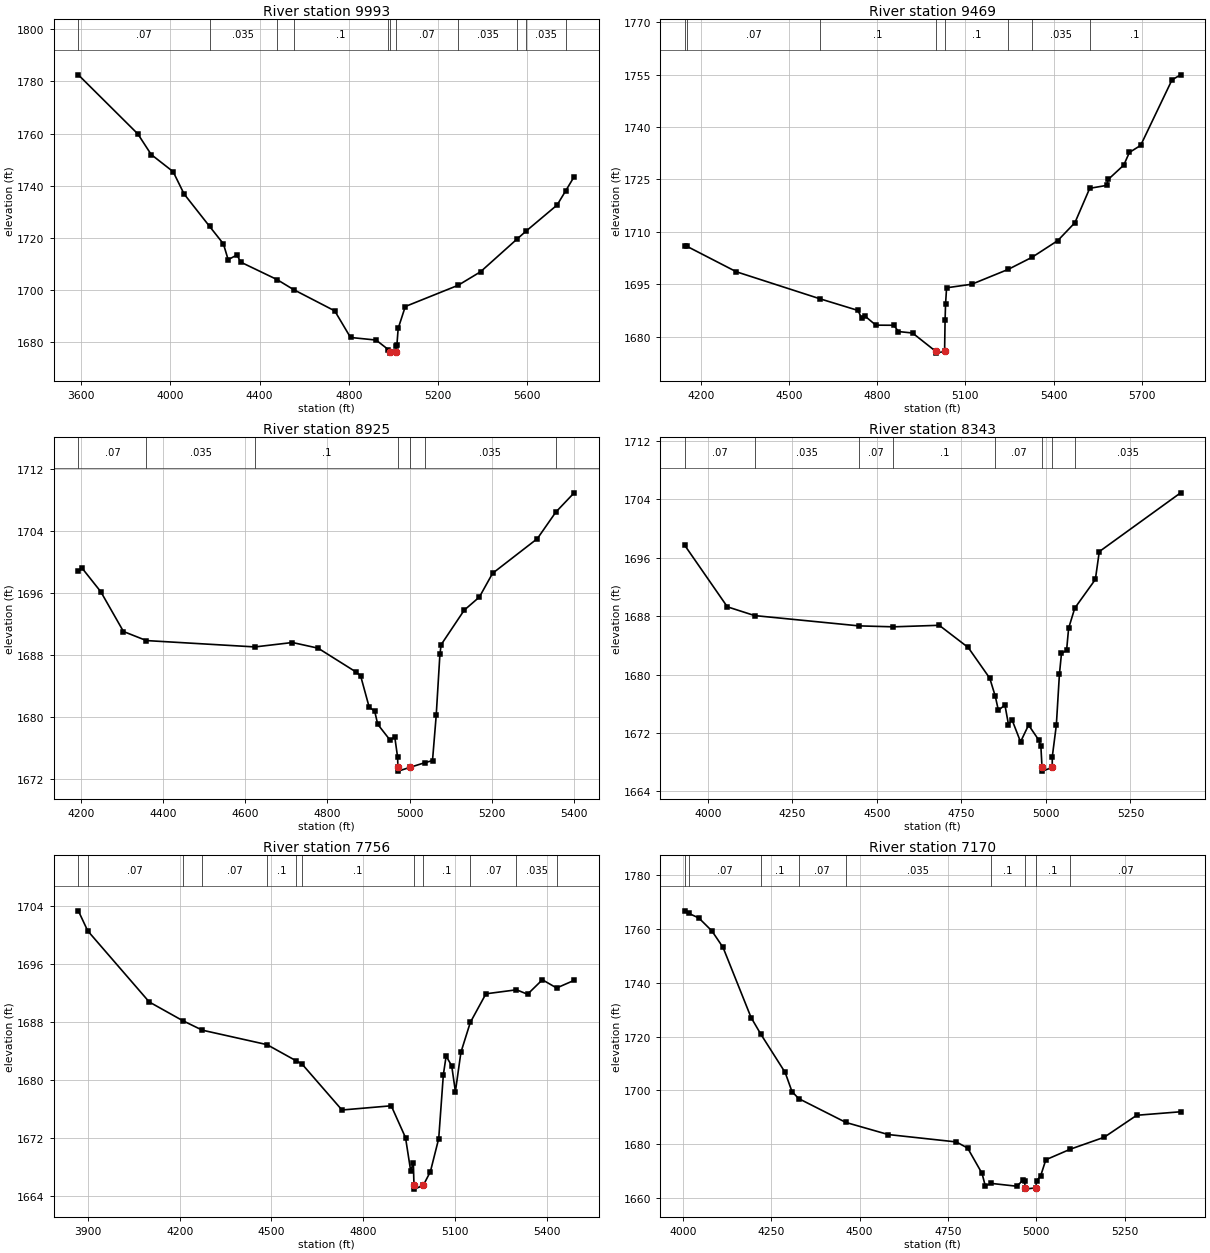
Type RM Length L Ch R = 1 ,9993    ,524,524,524
BEGIN DESCRIPTION:
Goat Creek 16.0
END DESCRIPTION:
XS GIS Cut Line= 4
      1906725.08     13941996.14       1905783.1     13941829.19
        1905325.       13941875.      1904524.97       13941975.
#Sta/Elev= 30
  3587.3 1782.54  3853.9 1759.87  3914.1 1751.94  4012.3 1745.37  4061.6 1736.79
  4176.2 1724.32  4237.8 1717.66  4259.1 1711.59  4298.7  1713.4  4315.3 1710.65
    4478 1703.96  4552.4  1700.1    4737 1691.93  4807.8 1681.72  4922.3 1680.73
  4977.3 1677.07  4982.8 1676.21  4983.3 1675.71  5012.7 1676.21  5012.8 1678.51
  5015.8 1678.87  5021.5 1685.19  5053.4  1693.6  5290.3 1701.75  5390.7 1706.93
  5556.3 1719.64  5594.9 1722.54  5734.1 1732.56  5772.6 1738.01  5810.6 1743.44
#Mann= 11 ,-1 , 0
  3587.3     .07       0  4176.2    .035       0    4478     .07       0
  4552.4      .1       0  4977.3     .07       0  4982.8     .05       0
  5012.7     .07       0  5290.3    .035       0  5556.3      .1       0
  5594.9    .035       0  5772.6      .1       0
Bank Sta=4982.8,5012.7
XS Rating Curve= 0 ,0
Exp/Cntr=0.3,0.1

Type RM Length L Ch R = 1 ,9469    ,544,544,544
BEGIN DESCRIPTION:
Goat Creek 15.0
END DESCRIPTION:
XS GIS Cut Line= 3
      1905924.99       13941725.        1905125.       13941425.
      1904424.96     13941875.02
#Sta/Elev= 30
  4145.5 1705.92  4153.4 1705.81  4321.1 1698.54  4605.6  1690.8  4734.4 1687.48
  4747.1 1685.26    4760 1685.75  4795.3 1683.26  4856.7 1683.23  4872.1 1681.43
  4920.2 1681.01  4999.3 1675.75  4999.8 1675.25  5029.2 1675.75  5030.9 1684.79
  5032.5 1689.33    5036 1693.96  5121.6 1694.98    5246 1699.25  5327.1 1702.72
  5414.1 1707.47  5472.5  1712.6  5522.9 1722.45  5580.2 1723.28  5585.7 1724.98
  5638.7  1729.1  5657.8 1732.72  5696.1 1734.74  5802.8 1753.51  5832.1 1754.95
#Mann= 8 ,-1 , 0
  4145.5    .035       0  4153.4     .07       0  4605.6      .1       0
  4999.3     .05       0  5029.2      .1       0    5246      .1       0
  5327.1    .035       0  5522.9      .1       0
Bank Sta=4999.3,5029.2
XS Rating Curve= 0 ,0
Exp/Cntr=0.3,0.1

Type RM Length L Ch R = 1 ,8925    ,582,582,582
BEGIN DESCRIPTION:
Goat Creek 14.0
END DESCRIPTION:
XS GIS Cut Line= 3
      1905774.97     13941324.98        1905075.       13940925.
      1904674.99       13940925.
#Sta/Elev= 30
  4194.2 1698.82  4203.8 1699.18  4248.8 1696.17    4304 1691.03  4359.8 1689.86
  4623.9 1689.04    4715 1689.61  4777.4 1688.88  4870.7 1685.77  4881.1 1685.27
  4901.8 1681.25  4915.1 1680.76  4922.5 1679.05  4952.5 1677.01    4964 1677.41
  4970.9  1674.8  4971.7  1673.5  4972.2    1673  5001.8  1673.5  5036.5 1674.08
  5055.8 1674.36  5064.8 1680.19  5073.8 1688.08  5076.8 1689.33    5133 1693.79
  5169.8 1695.48    5202 1698.55  5310.8 1703.02  5355.8 1706.45  5400.4 1708.94
#Mann= 7 ,-1 , 0
  4194.2     .07       0  4359.8    .035       0  4623.9      .1       0
  4971.7     .05       0  5001.8      .1       0  5036.5    .035       0
  5355.8     .07       0
Bank Sta=4971.7,5001.8
XS Rating Curve= 0 ,0
Exp/Cntr=0.3,0.1

Type RM Length L Ch R = 1 ,8343    ,587,587,587
BEGIN DESCRIPTION:
Goat Creek 13.0
END DESCRIPTION:
XS GIS Cut Line= 3
      1905874.98     13941174.97        1905175.       13940375.
      1904774.99       13940325.
#Sta/Elev= 30
  3932.2 1697.69    4058 1689.28  4138.7 1688.08  4447.1 1686.67    4549 1686.54
  4684.5 1686.75  4770.2 1683.71    4834  1679.5  4850.4 1677.01  4859.5 1675.09
  4878.7 1675.85  4889.3 1673.16  4899.9 1673.79    4925 1670.79  4948.7 1673.09
  4978.6 1671.05  4985.1 1670.16  4988.5 1667.28    4989 1666.78  5018.7 1667.28
  5018.8 1668.74  5030.8 1673.08  5039.9 1680.04    5046  1682.9  5061.1 1683.31
  5067.1 1686.34  5085.3  1689.1  5146.2 1693.03  5157.8 1696.84  5398.3 1704.89
#Mann= 8 ,-1 , 0
  3932.2     .07       0  4138.7    .035       0  4447.1     .07       0
    4549      .1       0  4850.4     .07       0  4988.5     .05       0
  5018.7     .07       0  5085.3    .035       0
Bank Sta=4988.5,5018.7
XS Rating Curve= 0 ,0
Exp/Cntr=0.3,0.1

Type RM Length L Ch R = 1 ,7756    ,586,586,586
BEGIN DESCRIPTION:
Goat Creek 12.0
END DESCRIPTION:
XS GIS Cut Line= 3
      1906475.02     13941025.02        1905675.       13940225.
      1905737.94     13939739.77
#Sta/Elev= 30
  3868.6 1703.28  3899.4 1700.52  4100.3 1690.75  4209.2 1688.19  4273.7 1686.87
  4485.3 1684.88  4579.5 1682.68  4599.2 1682.24  4730.4 1675.89  4891.4 1676.47
  4938.1 1672.09    4955 1667.51  4963.7 1668.67  4965.7 1665.51  4966.2 1665.01
  4995.9 1665.51  5019.4 1667.42  5046.6 1671.97  5061.7 1680.73  5070.8  1683.3
    5089 1681.97  5101.1 1678.43  5119.2 1683.83  5149.8 1687.93  5200.9 1691.87
  5300.8 1692.42    5337 1691.81  5385.4  1693.8    5432 1692.67  5489.3 1693.72
#Mann= 12 ,-1 , 0
  3868.6    .035       0  3899.4     .07       0  4209.2    .035       0
  4273.7     .07       0  4485.3      .1       0  4579.5     .07       0
  4599.2      .1       0  4965.7     .05       0  4995.9      .1       0
  5149.8     .07       0  5300.8    .035       0    5432     .07       0
Bank Sta=4965.7,4995.9
XS Rating Curve= 0 ,0
Exp/Cntr=0.3,0.1

Type RM Length L Ch R = 1 ,7170    ,502,502,502
BEGIN DESCRIPTION:
Goat Creek 11.0
END DESCRIPTION:
XS GIS Cut Line= 3
      1907025.04     13940725.03        1906225.       13940125.
      1906024.98     13939774.97
#Sta/Elev= 30
  4005.4 1766.66    4016 1765.76  4045.2 1763.99  4082.2 1759.18  4113.7 1753.05
    4193 1727.04  4220.7 1720.83  4289.4 1706.65  4308.7 1699.57  4327.6 1696.96
  4461.4 1688.09  4580.9 1683.61  4773.7 1680.86  4805.8 1678.59  4846.6 1669.17
  4855.8 1664.51  4871.8 1665.48  4945.2 1664.41  4962.3 1666.65  4967.2 1666.35
  4968.6 1663.84  4969.1 1663.34  4998.9 1663.84  5000.8 1666.35  5012.6  1668.3
  5027.1 1674.24  5096.9 1678.19  5192.3  1682.6  5284.4 1690.76  5408.6 1692.06
#Mann= 9 ,-1 , 0
  4005.4    .035       0    4016     .07       0  4220.7      .1       0
  4327.6     .07       0  4461.4    .035       0  4871.8      .1       0
  4968.6     .05       0  4998.9      .1       0  5096.9     .07       0
Bank Sta=4968.6,4998.9
XS Rating Curve= 0 ,0
Exp/Cntr=0.3,0.1

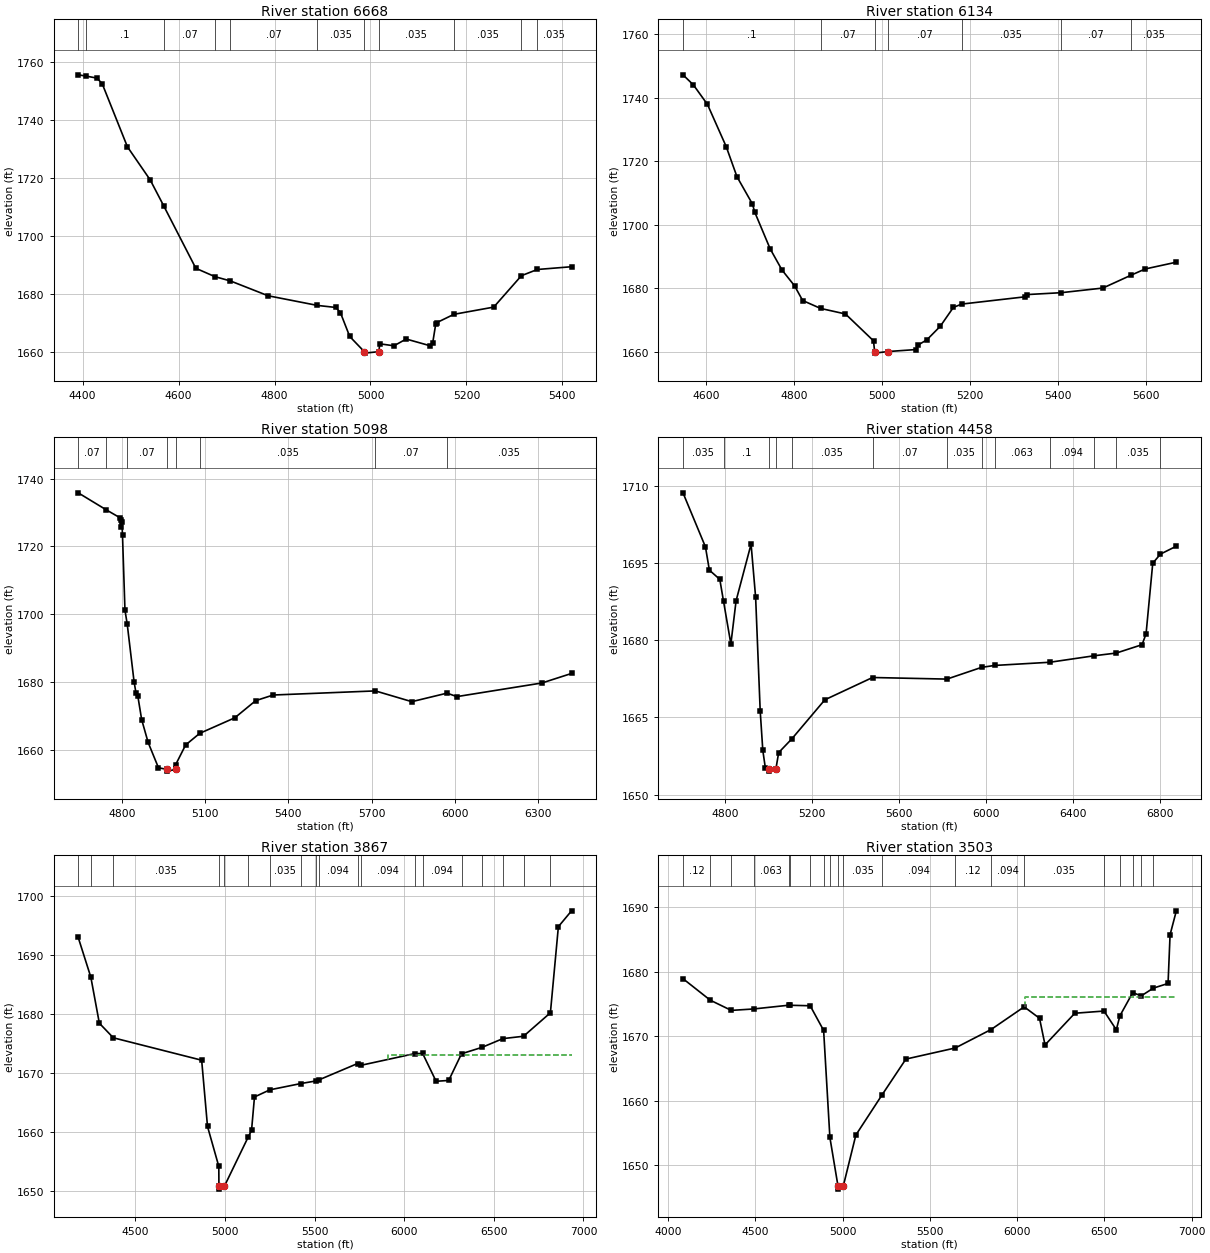
Type RM Length L Ch R = 1 ,6668    ,534,534,534
BEGIN DESCRIPTION:
Goat Creek 10.0
END DESCRIPTION:
XS GIS Cut Line= 3
      1907225.03     13940275.01        1906675.       13940025.
      1906375.04     13939725.04
#Sta/Elev= 30
  4390.8 1755.47  4406.4 1755.06  4429.8 1754.35  4440.7 1752.46  4493.4  1730.7
  4540.8 1719.34  4569.2 1710.35    4636 1688.92  4675.9 1686.04  4708.1 1684.57
  4786.7 1679.47  4889.4 1676.15  4927.8 1675.45  4937.3 1673.69  4956.8 1665.46
  4987.2 1660.24  4987.7 1659.74  5017.6 1660.24  5019.3 1662.95    5049 1662.26
  5074.5 1664.59  5123.4 1662.32  5129.8 1663.31  5136.1 1669.79  5138.1 1670.22
    5174 1673.09    5257 1675.57  5314.7 1686.38  5347.8 1688.51  5419.2 1689.46
#Mann= 11 ,-1 , 0
  4390.8     .07       0  4406.4      .1       0  4569.2     .07       0
  4675.9    .035       0  4708.1     .07       0  4889.4    .035       0
  4987.2     .05       0  5017.6    .035       0    5174    .035       0
  5314.7     .07       0  5347.8    .035       0
Bank Sta=4987.2,5017.6
XS Rating Curve= 0 ,0
Exp/Cntr=0.3,0.1

Type RM Length L Ch R = 1 ,6134    ,1036,1036,1036
BEGIN DESCRIPTION:
Goat Creek 9.0
END DESCRIPTION:
XS GIS Cut Line= 4
        1907275.     13940124.99        1907075.       13939725.
      1907000.64     13939662.81      1906425.02       13939625.
#Sta/Elev= 30
  4547.9 1747.23  4571.6 1744.05  4603.5 1737.92    4646 1724.67  4670.6 1715.15
  4705.8 1706.55  4710.8 1704.06    4746 1692.46  4772.8 1685.82  4801.4 1680.83
  4819.8 1676.21  4860.5 1673.72  4917.1 1671.97  4980.8 1663.52  4983.3 1660.15
  4983.8 1659.65  5013.7 1660.15  5077.9 1660.78  5082.1  1662.2  5102.1 1663.84
  5132.5  1668.1  5162.2 1674.03    5181 1675.08  5324.4 1677.36    5330 1678.08
  5407.2 1678.67    5502 1680.13  5566.2 1684.19    5598 1686.13  5668.9 1688.27
#Mann= 7 ,-1 , 0
  4547.9      .1       0  4860.5     .07       0  4983.3     .05       0
  5013.7     .07       0    5181    .035       0  5407.2     .07       0
  5566.2    .035       0
Bank Sta=4983.3,5013.7
XS Rating Curve= 0 ,0
Exp/Cntr=0.3,0.1

Type RM Length L Ch R = 1 ,5098    ,640,640,640
BEGIN DESCRIPTION:
Goat Creek 8.0
END DESCRIPTION:
XS GIS Cut Line= 4
        1907875.       13939275.      1907720.99     13939005.49
      1907513.94     13939005.53      1906257.49     13939087.71
#Sta/Elev= 30
  4643.4 1735.79    4743 1730.85  4794.1 1728.44  4796.3 1725.83    4798 1727.75
  4800.7  1727.1  4802.9 1723.27  4811.7 1701.31    4820 1697.06  4844.5 1680.22
  4851.3 1676.93  4857.9 1676.05  4871.9 1669.02  4895.2  1662.3  4932.4 1654.84
  4963.9 1654.35  4964.4 1653.85  4994.4 1654.35  4994.5 1655.78  5030.2 1661.55
  5080.9 1664.97  5207.3 1669.55  5282.5  1674.6  5345.6 1676.26  5713.5 1677.47
  5844.7  1674.3  5971.6 1676.81    6007 1675.79  6313.7 1679.81    6420 1682.61
#Mann= 8 ,-1 , 0
  4643.4     .07       0    4743      .1       0    4820     .07       0
  4963.9     .05       0  4994.4     .07       0  5080.9    .035       0
  5713.5     .07       0  5971.6    .035       0
Bank Sta=4963.9,4994.4
XS Rating Curve= 0 ,0
Exp/Cntr=0.3,0.1

Type RM Length L Ch R = 1 ,4458    ,591,591,591
BEGIN DESCRIPTION:
Goat Creek 7.0
END DESCRIPTION:
XS GIS Cut Line= 3
      1908074.98       13938425.        1907675.       13938425.
      1905852.86     13938849.89
#Sta/Elev= 30
  4604.7 1708.62  4708.1 1698.12  4726.1 1693.61  4774.1 1691.82  4791.2 1687.59
  4825.1 1679.27  4849.1 1687.66  4918.1 1698.66  4939.1  1688.3  4960.1 1666.28
  4972.1 1658.61  4984.1 1655.11  5002.2 1655.08  5002.7 1654.58  5032.7 1655.08
  5045.1 1658.18  5105.6 1660.84  5257.7 1668.43  5477.3 1672.76  5819.6 1672.45
  5979.2 1674.73  6039.1  1675.1  6293.3 1675.72  6497.3 1676.98  6599.3 1677.51
  6717.8 1679.13  6736.3 1681.23  6767.1 1694.95  6802.5 1696.72  6875.7 1698.26
#Mann= 13 ,-1 , 0
  4604.7    .035       0  4791.2      .1       0  5002.2     .05       0
  5032.7      .1       0  5105.6    .035       0  5477.3     .07       0
  5819.6    .035       0  5979.2    .094       0  6039.1    .063       0
  6293.3    .094       0  6497.3     .12       0  6599.3    .035       0
  6802.5    .094       0
Bank Sta=5002.2,5032.7
XS Rating Curve= 0 ,0
Exp/Cntr=0.3,0.1

Type RM Length L Ch R = 1 ,3867    ,364,364,364
BEGIN DESCRIPTION:
Goat Creek 6.0
END DESCRIPTION:
XS GIS Cut Line= 4
      1908394.58     13937601.43      1907621.56     13937879.39
      1906663.63      13938302.5      1905894.62     13938736.68
#Sta/Elev= 30
  4181.8 1693.03  4252.3 1686.29  4299.7 1678.49  4377.7 1676.02  4870.4 1672.22
    4903 1660.99    4966 1654.22  4966.7 1650.87  4967.2 1650.37  4997.3 1650.87
  5131.4 1659.29  5148.6 1660.32    5165 1665.99  5250.7  1667.2  5422.7 1668.26
  5510.7 1668.72  5526.4 1668.91  5740.1 1671.66  5759.2 1671.36  6058.7 1673.34
  6103.1 1673.36    6178 1668.65  6248.4 1668.79  6319.8 1673.31  6435.1 1674.41
  6550.4 1675.88  6665.7 1676.28  6815.6 1680.26  6860.1 1694.86  6933.6 1697.54
#Mann= 19 ,-1 , 0
  4181.8    .063       0  4252.3    .094       0  4377.7    .035       0
  4966.7    .035       0  4997.3    .035       0  5131.4    .094       0
  5250.7    .035       0  5422.7    .094       0  5510.7     .12       0
  5526.4    .094       0  5740.1    .035       0  5759.2    .094       0
  6058.7    .035       0  6103.1    .094       0  6319.8    .063       0
  6435.1    .094       0  6550.4     .12       0  6665.7    .035       0
  6815.6     .12       0
#XS Ineff= 2 , 0
                         5906.98         1673.13
Permanent Ineff=
       F       F
Bank Sta=4966.7,4997.3
XS Rating Curve= 0 ,0
Exp/Cntr=0.3,0.1

Type RM Length L Ch R = 1 ,3503    ,707,707,707
BEGIN DESCRIPTION:
Goat Creek 5.0
END DESCRIPTION:
XS GIS Cut Line= 4
      1908388.12     13937139.77       1907571.1     13937564.86
      1906984.33     13937880.57      1905967.63     13938590.79
#Sta/Elev= 30
  4084.9 1678.89  4241.2 1675.56  4361.7 1673.98  4489.3  1674.2  4690.1 1674.78
  4700.8 1674.77  4813.8  1674.7  4890.9 1670.88  4926.8  1654.3  4973.1  1646.8
  4973.6  1646.3  5003.8  1646.8  5075.7 1654.68  5224.9 1660.86  5362.4 1666.44
  5645.3 1668.16  5850.7 1671.02  6040.3 1674.53  6128.3 1672.76  6159.8 1668.63
  6330.6 1673.54  6497.8 1673.88  6568.4 1670.98  6588.9 1673.14  6662.1 1676.72
  6711.9 1676.24  6780.5 1677.43  6864.9 1678.15  6876.5  1685.7  6912.4  1689.4
#Mann= 20 ,-1 , 0
  4084.9     .12       0  4241.2    .063       0  4361.7    .035       0
  4489.3    .063       0  4690.1     .12       0  4700.8    .063       0
  4813.8    .035       0  4890.9    .063       0  4926.8    .035       0
  4973.1    .035       0  5003.8    .035       0  5224.9    .094       0
  5645.3     .12       0  5850.7    .094       0  6040.3    .035       0
  6497.8    .063       0  6588.9    .094       0  6662.1     .12       0
  6711.9    .063       0  6780.5    .035       0
#XS Ineff= 2 , 0
                         6042.64         1676.07
Permanent Ineff=
       F       F
Bank Sta=4973.1,5003.8
XS Rating Curve= 0 ,0
Exp/Cntr=0.3,0.1

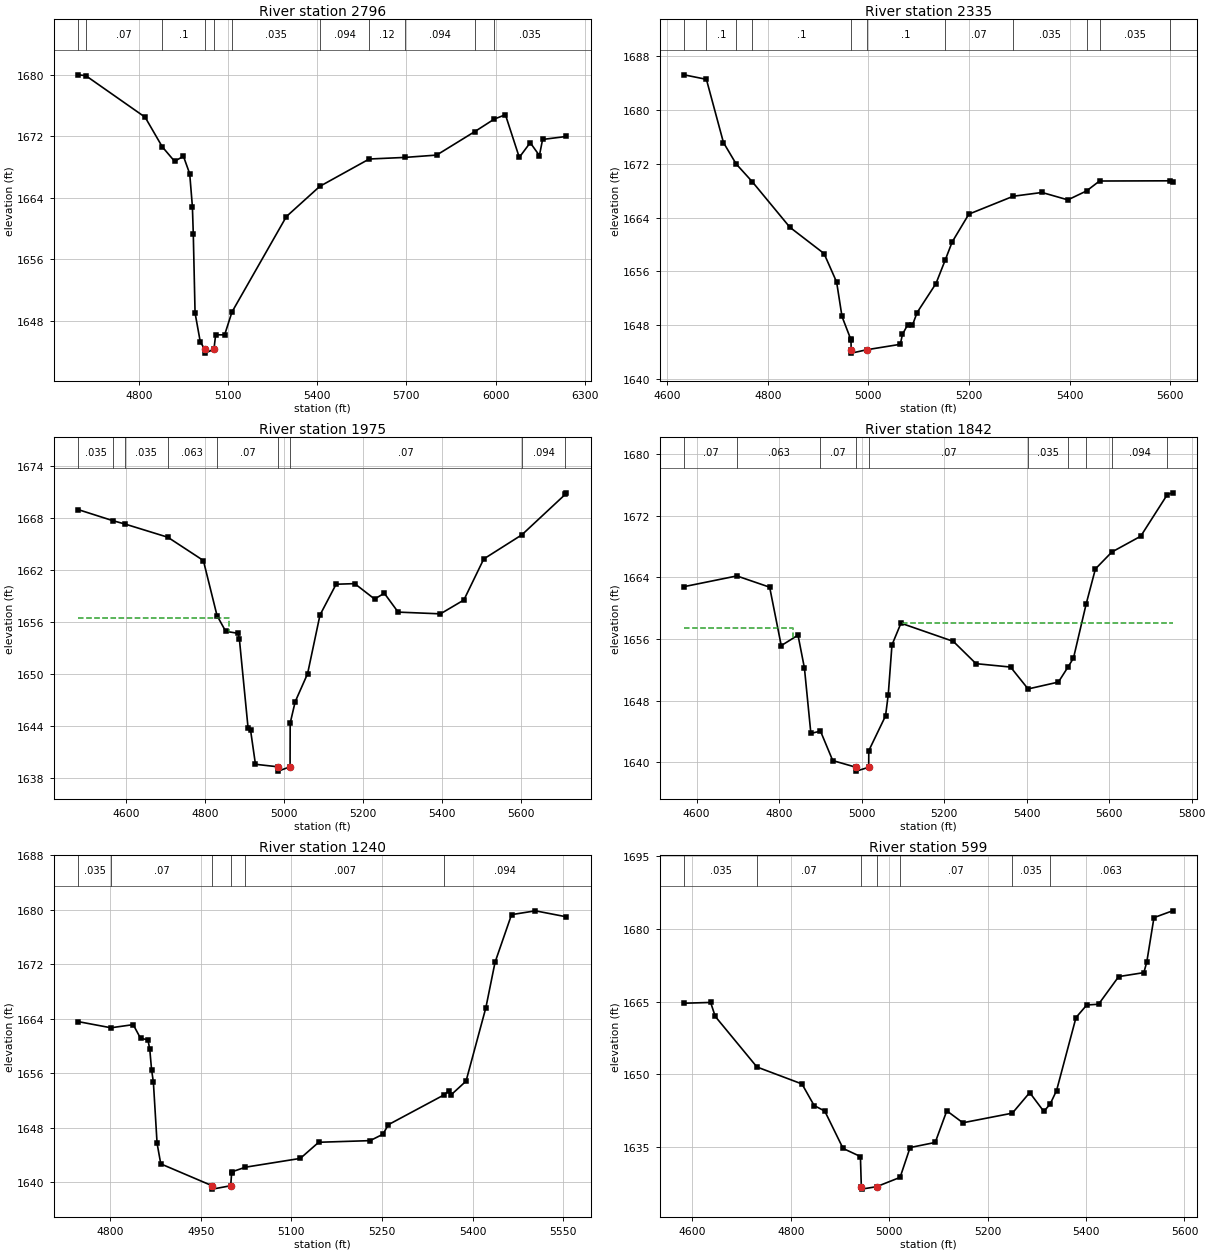
Type RM Length L Ch R = 1 ,2796    ,461,461,461
BEGIN DESCRIPTION:
Goat Creek 4.0
END DESCRIPTION:
XS GIS Cut Line= 4
        1907025.     13936874.97        1907025.       13937275.
      1906977.99     13937826.94      1906398.16     13938198.45
#Sta/Elev= 30
  4595.5 1679.96  4621.5 1679.86  4821.3 1674.46  4878.9 1670.62  4920.3 1668.74
  4950.3 1669.38  4971.3 1667.11  4980.3 1662.85  4983.3 1659.33  4989.3 1649.04
  5006.9 1645.28  5022.1 1644.33  5022.6 1643.83  5052.8 1644.33  5058.5 1646.21
  5088.7  1646.2  5113.4 1649.17  5296.4 1661.56  5408.7 1665.48  5574.9 1669.03
  5695.6 1669.24  5801.7 1669.54  5929.5 1672.58  5995.8 1674.22    6033 1674.78
  6079.6 1669.24  6116.4 1671.15  6147.3 1669.48    6158 1671.57  6238.1 1671.96
#Mann= 11 ,-1 , 0
  4595.5    .035       0  4621.5     .07       0  4878.9      .1       0
  5022.1     .05       0  5052.8      .1       0  5113.4    .035       0
  5408.7    .094       0  5574.9     .12       0  5695.6    .094       0
  5929.5    .063       0  5995.8    .035       0
Bank Sta=5022.1,5052.8
XS Rating Curve= 0 ,0
Exp/Cntr=0.3,0.1

Type RM Length L Ch R = 1 ,2335    ,360,360,360
BEGIN DESCRIPTION:
Goat Creek 3.0
END DESCRIPTION:
XS GIS Cut Line= 3
      1906824.98     13936975.03      1906619.19     13937294.07
      1906698.24     13937879.91
#Sta/Elev= 30
  4633.7 1685.19  4678.1 1684.52    4712 1675.13  4737.2 1671.96  4769.3 1669.31
    4844 1662.55  4911.9 1658.65  4936.9 1654.42  4947.6  1649.3  4964.6    1646
  4965.4 1645.78  4965.9 1644.36  4966.4 1643.86  4996.6 1644.36  5063.5 1645.17
  5067.7 1646.64  5078.4  1648.1  5087.7 1648.02  5096.8 1649.88  5134.4  1654.2
  5152.8 1657.69  5166.5 1660.36  5199.7  1664.5    5288 1667.16  5345.1 1667.72
  5396.5 1666.62  5433.7 1667.95  5459.4 1669.42  5598.6 1669.45  5604.5 1669.32
#Mann= 11 ,-1 , 0
  4633.7     .07       0  4678.1      .1       0  4737.2    .035       0
  4769.3      .1       0  4965.9     .05       0  4996.6      .1       0
  5152.8     .07       0    5288    .035       0  5433.7    .094       0
  5459.4    .035       0  5598.6    .063       0
Bank Sta=4965.9,4996.6
XS Rating Curve= 0 ,0
Exp/Cntr=0.3,0.1

Type RM Length L Ch R = 1 ,1975    ,133,133,133
BEGIN DESCRIPTION:
Goat Creek 2.1
END DESCRIPTION:
XS GIS Cut Line= 3
      1906663.04     13936893.94      1906417.71      13937059.2
      1906140.18     13937957.71
#Sta/Elev= 30
  4478.3    1669  4567.5  1667.7  4596.2 1667.34  4705.7  1665.8  4795.7 1663.11
  4830.3 1656.74  4852.2 1654.93  4883.6  1654.7  4886.7 1654.09  4908.7 1643.82
    4915 1643.55  4927.5 1639.57  4984.4 1639.28  4984.9 1638.78  5015.1 1639.28
  5015.4 1644.32    5028 1646.79  5059.4 1650.03  5090.8 1656.81  5131.6 1660.37
  5178.7 1660.44    5229 1658.66  5253.6 1659.33  5288.6 1657.15  5395.7 1656.95
    5455 1658.55  5505.3 1663.29  5601.8 1666.08  5711.3 1670.74  5714.5 1670.93
#Mann= 9 ,-1 , 0
  4478.3    .035       0  4567.5    .063       0  4596.2    .035       0
  4705.7    .063       0  4830.3     .07       0  4984.4     .05       0
  5015.1     .07       0  5601.8    .094       0  5711.3    .035       0
#XS Ineff= 2 , 0
         4859.43 1656.43
Permanent Ineff=
       F       F
Bank Sta=4984.4,5015.1
XS Rating Curve= 0 ,0
Exp/Cntr=0.3,0.1

Type RM Length L Ch R = 1 ,1842    ,602,602,602
BEGIN DESCRIPTION:
Goat Creek 2.0
END DESCRIPTION:
XS GIS Cut Line= 3
       1906338.1     13936853.34      1906160.78     13937471.47
      1905926.86     13937959.33
#Sta/Elev= 30
  4569.5  1662.8  4697.5 1664.19    4777 1662.73  4805.1 1655.15  4845.7 1656.51
  4861.3 1652.24  4876.9 1643.76  4900.2 1644.06  4929.9 1640.24  4986.4 1639.37
  4986.9 1638.87  5017.1 1639.37  5017.3 1641.52  5057.9 1646.03  5064.5  1648.8
  5073.5 1655.24  5095.3 1658.06  5222.2  1655.7  5277.2 1652.81    5361 1652.37
  5403.5 1649.53  5476.9 1650.42  5500.8 1652.42  5513.5 1653.53  5544.3 1660.56
  5566.7  1665.1  5606.5 1667.29  5676.5 1669.34  5741.1 1674.75  5753.6 1674.97
#Mann= 10 ,-1 , 0
  4569.5     .07       0  4697.5    .063       0  4900.2     .07       0
  4986.4     .05       0  5017.1     .07       0  5403.5    .035       0
  5500.8     .07       0  5544.3    .035       0  5606.5    .094       0
  5741.1    .035       0
#XS Ineff= 2 , 0
         4834.11  1657.5 5100.43         1658.06
Permanent Ineff=
       F       F
Bank Sta=4986.4,5017.1
XS Rating Curve= 0 ,0
Exp/Cntr=0.3,0.1

Type RM Length L Ch R = 1 ,1240    ,641,641,641
BEGIN DESCRIPTION:
Goat Creek 1.1
END DESCRIPTION:
XS GIS Cut Line= 2
       1905751.3     13937175.55       1905622.5     13937973.42
#Sta/Elev= 30
    4747 1663.57  4801.6 1662.66  4838.4 1663.12  4850.6 1661.11  4862.7  1660.9
  4865.8 1659.51  4868.8 1656.51  4871.8 1654.66  4877.9  1645.7    4884 1642.68
  4968.9 1639.47  4969.4 1638.97  4999.7 1639.47  5001.3 1641.34  5002.5 1641.53
  5024.1 1642.19  5114.9 1643.48  5145.3 1645.85  5230.4 1646.09  5251.4 1647.02
  5260.8 1648.44  5352.8 1652.81  5361.1 1653.44  5364.1 1652.79  5389.1 1654.82
  5421.9  1665.6  5437.1 1672.27  5464.4 1679.27  5503.9 1679.83  5555.2 1678.95
#Mann= 6 ,-1 , 0
    4747    .035       0  4801.6     .07       0  4968.9     .05       0
  4999.7     .07       0  5024.1    .007       0  5352.8    .094       0
Bank Sta=4968.9,4999.7
XS Rating Curve= 0 ,0
Exp/Cntr=0.3,0.1

Type RM Length L Ch R = 1 ,599     ,0,0,0
BEGIN DESCRIPTION:
Goat Creek 1.0
END DESCRIPTION:
XS GIS Cut Line= 4
      1905825.02     13937075.01        1905425.       13936975.
      1905231.31     13937136.55      1905075.01     13937424.97
#Sta/Elev= 30
  4583.1 1664.66  4637.1 1664.82  4646.4 1661.95  4731.2 1651.53  4822.7 1648.04
  4847.4  1643.6    4869 1642.46  4906.2 1634.77  4941.5  1633.1  4943.3 1626.89
  4943.8 1626.39  4974.2 1626.89  5022.1 1628.81  5042.4 1634.95  5093.5    1636
    5117 1642.51  5149.7 1640.05  5250.2 1642.03  5285.5 1646.26  5314.2 1642.38
  5327.1 1643.91  5340.1 1646.69  5379.6 1661.72  5401.5  1664.3  5425.4 1664.45
  5466.3 1670.14  5517.5 1670.96  5523.5  1673.2    5538 1682.28  5575.7 1683.68
#Mann= 7 ,-1 , 0
  4583.1    .035       0  4731.2     .07       0  4943.3     .05       0
  4974.2     .07       0  5022.1     .07       0  5250.2    .035       0
  5327.1    .063       0
Bank Sta=4943.3,4974.2
XS Rating Curve= 0 ,0
Exp/Cntr=0.3,0.1

Chan Stop Cuts=-1
Use User Specified Reach Order=0
Composite Channel Slope=5