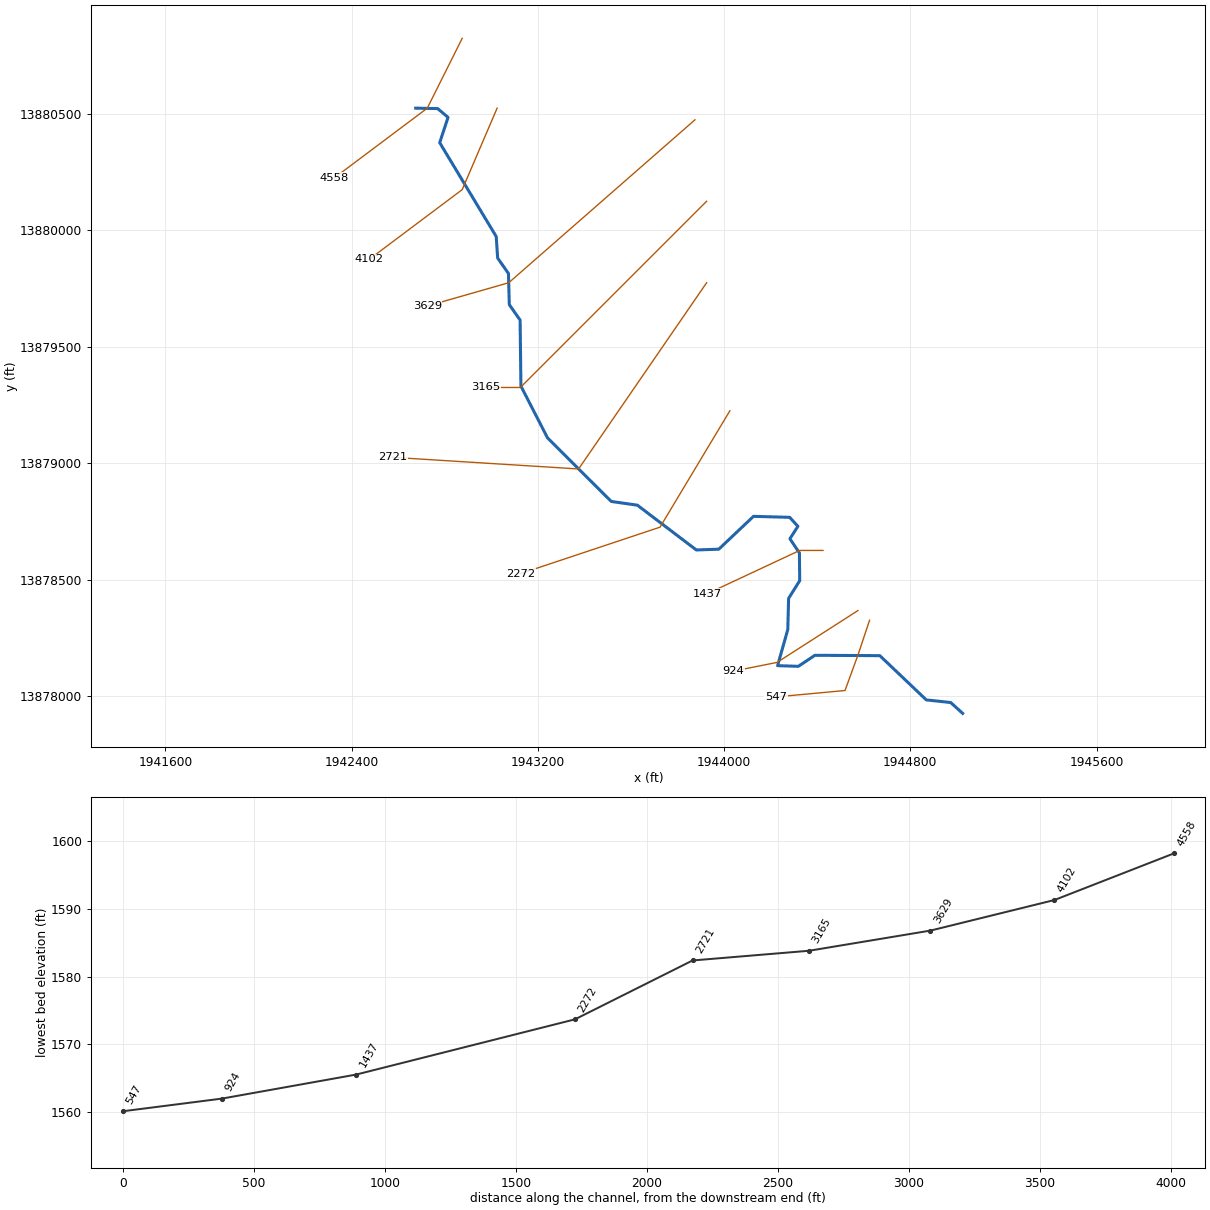
--- Happy Hollow.prj (project) ---

Proj Title=Happy Hollow Base Level Engineering
Current Plan=p01
Default Exp/Contr=0.3,0.1
English Units
Geom File=g01
Flow File=f01
Plan File=p01
BEGIN DESCRIPTION:
Happy Hollow
END DESCRIPTION:

--- Happy Hollow.p01 (plan) ---

Plan Title=Multiple Run
Short Identifier=Multiple
Geom File=g01
Flow File=f01
Subcritical Flow
K Sum by GR= 0
Std Step Tol= 0.01
Critical Tol= 0.01
Num of Std Step Trials= 20
Max Error Tol= 0.3
Flow Tol Ratio= 0.001
Split Flow NTrial= 30
Split Flow Tol= 0.02
Split Flow Ratio= 0.02
Log Output Level= 0
Friction Slope Method= 1
Unsteady Friction Slope Method= 2
Unsteady Bridges Friction Slope Method= 1
Parabolic Critical Depth
Global Vel Dist=  1 , 1 , 1
Global Log Level= 0
CheckData=True
Encroach Param= -1, 0, 0, 0
BEGIN DESCRIPTION:
Multiple Run
END DESCRIPTION:

--- Happy Hollow.f01 (steady flow) ---

Flow Title=Multiple
Number of Profiles=7
Profile Names=10-year,25-year,50-year,1pct_min,100-year,1pct_plu,500-year
River Rch & RM= Happy Hollow,Reach-1,4558
    2050    3610    5144    3539    7061   14089   13143
Boundary for River Rch & Prof#=Happy Hollow,Reach-1,1
Up Type=0
Dn Type=3
Dn Slope=0.005
Boundary for River Rch & Prof#=Happy Hollow,Reach-1,2
Up Type=0
Dn Type=3
Dn Slope=0.005
Boundary for River Rch & Prof#=Happy Hollow,Reach-1,3
Up Type=0
Dn Type=3
Dn Slope=0.005
Boundary for River Rch & Prof#=Happy Hollow,Reach-1,4
Up Type=0
Dn Type=3
Dn Slope=0.005
Boundary for River Rch & Prof#=Happy Hollow,Reach-1,5
Up Type=0
Dn Type=3
Dn Slope=0.005
Boundary for River Rch & Prof#=Happy Hollow,Reach-1,6
Up Type=0
Dn Type=3
Dn Slope=0.005
Boundary for River Rch & Prof#=Happy Hollow,Reach-1,7
Up Type=0
Dn Type=3
Dn Slope=0.005

--- Happy Hollow.g01 (geometry) ---

Geom Title=Existing Conditions

River Reach=Happy Hollow,Reach-1
Reach XY= 30
      1942675.00     13880525.00      1942769.71     13880523.15
      1942814.10     13880485.41      1942778.37     13880376.74
      1943021.17     13879973.42      1943027.36     13879880.98
      1943073.77     13879814.49      1943077.27     13879680.94
      1943123.78     13879614.50      1943127.24     13879330.93
      1943241.64     13879108.32      1943515.21     13878835.52
      1943627.42     13878819.46      1943880.90     13878626.97
      1943977.43     13878630.40      1944126.47     13878771.47
      1944281.82     13878767.20      1944317.13     13878728.62
      1944282.81     13878675.11      1944323.64     13878614.56
      1944324.95     13878495.04      1944277.27     13878419.06
      1944273.77     13878285.51      1944229.96     13878129.96
      1944318.92     13878127.12      1944390.21     13878174.48
      1944669.15     13878172.94      1944868.82     13877982.84
      1944973.59     13877971.61      1945025.00     13877925.00

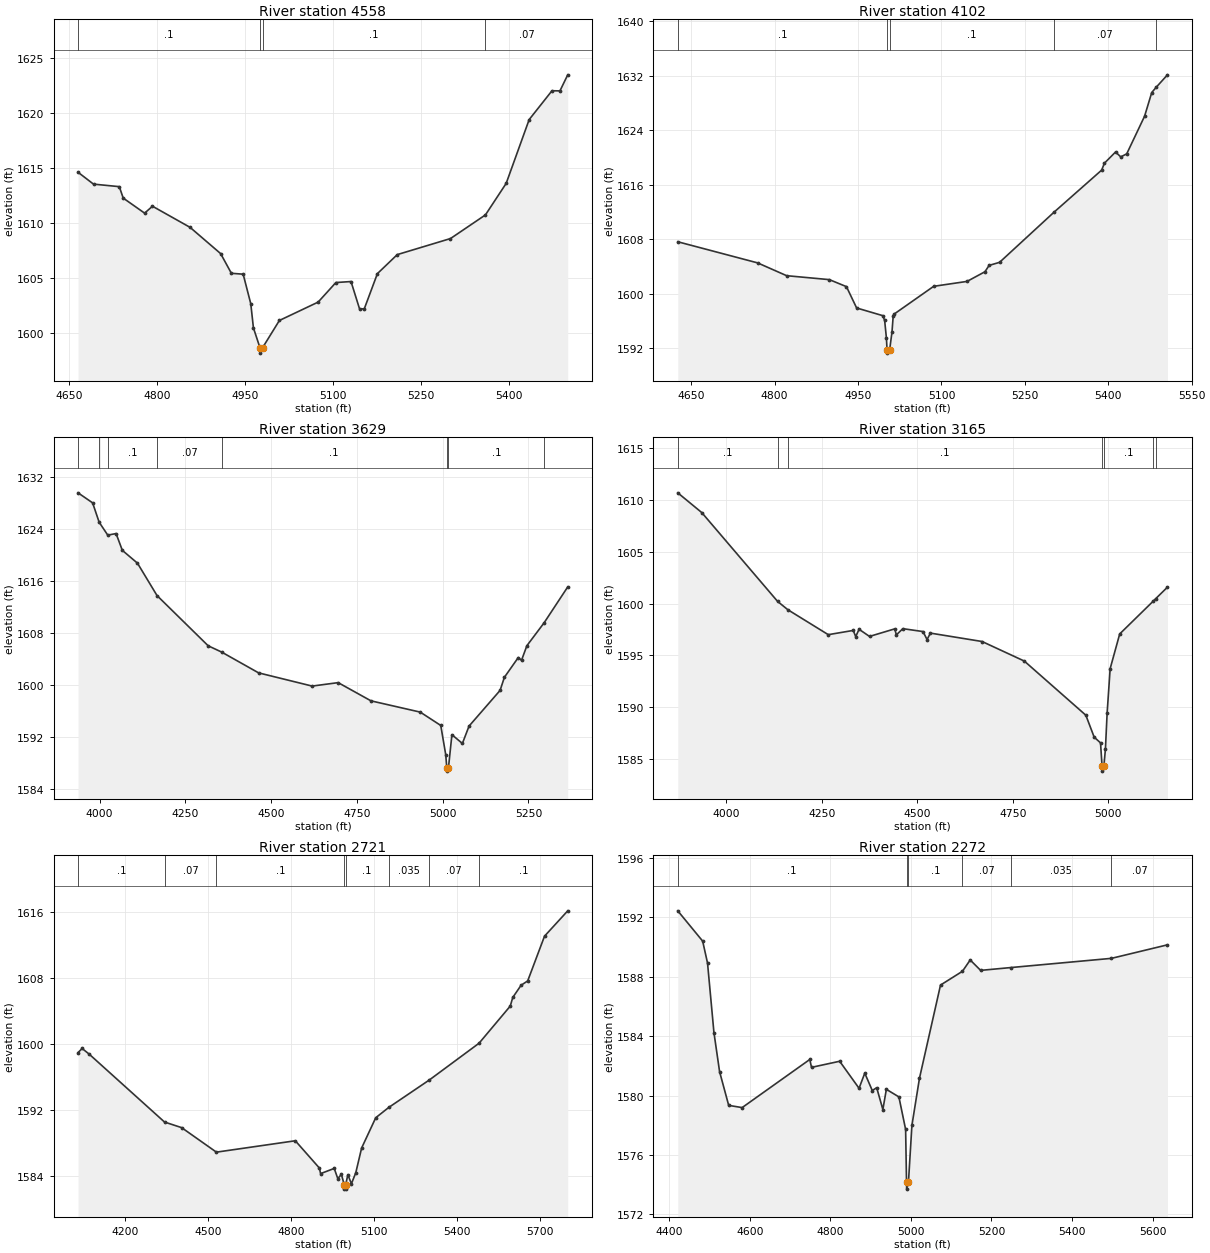
Type RM Length L Ch R = 1,4558,456,456,456
BEGIN DESCRIPTION:
Stream0690 9.0
END DESCRIPTION:
XS GIS Cut Line= 3
      1942874.98     13880824.96      1942725.00     13880525.00
      1942324.97     13880224.98
#Sta/Elev= 30
  4665.4 1614.64  4691.8 1613.56  4735.8 1613.33  4742.5 1612.29  4779.0 1610.92
  4792.4 1611.55  4856.5 1609.63  4908.7 1607.24  4927.0 1605.45  4947.1 1605.37
  4960.1 1602.68  4964.6 1600.49  4975.7 1598.69  4976.0 1598.19  4980.3 1598.69
  5008.9 1601.16  5075.0 1602.83  5105.3 1604.61  5131.1 1604.70  5145.8 1602.19
  5153.8 1602.23  5176.1 1605.42  5210.0 1607.15  5300.8 1608.61  5360.4 1610.76
  5395.8 1613.63  5435.0 1619.43  5473.9 1622.05  5487.5 1622.04  5500.8 1623.50
#Mann=4,-1,0
  4665.4     0.1       0  4975.7    0.05       0  4980.3     0.1       0
  5360.4    0.07       0
Bank Sta=4975.7,4980.3
Exp/Cntr=0.3,0.1

Type RM Length L Ch R = 1,4102,473,473,473
BEGIN DESCRIPTION:
Stream0690 8.0
END DESCRIPTION:
XS GIS Cut Line= 3
      1943024.99     13880524.97      1942875.00     13880175.00
      1942474.96     13879874.97
#Sta/Elev= 30
  4625.7 1607.66  4769.3 1604.56  4821.5 1602.68  4898.4 1602.10  4929.1 1601.07
  4947.4 1597.94  4994.5 1596.81  4997.8 1596.11  5001.0 1593.49  5002.1 1591.81
  5002.5 1591.31  5006.8 1591.81  5011.0 1594.41  5013.2 1596.79  5015.3 1597.07
  5086.0 1601.12  5146.0 1601.84  5178.2 1603.26  5185.7 1604.19  5204.5 1604.64
  5302.8 1612.03  5388.1 1618.18  5393.1 1619.20  5413.1 1620.84  5422.5 1620.12
  5433.2 1620.57  5465.3 1626.09  5478.2 1629.57  5486.5 1630.37  5506.5 1632.17
#Mann=5,-1,0
  4625.7     0.1       0  5002.1    0.05       0  5006.8     0.1       0
  5302.8    0.07       0  5486.5     0.1       0
Bank Sta=5002.1,5006.8
Exp/Cntr=0.3,0.1

Type RM Length L Ch R = 1,3629,464,464,464
BEGIN DESCRIPTION:
Stream0690 7.0
END DESCRIPTION:
XS GIS Cut Line= 3
      1943875.02     13880475.02      1943075.00     13879775.00
      1942725.05     13879675.01
#Sta/Elev= 30
  3937.4 1629.57  3979.9 1628.03  3998.9 1625.06  4024.0 1623.07  4048.3 1623.31
  4066.5 1620.73  4110.6 1618.76  4167.6 1613.78  4316.7 1606.06  4355.8 1605.10
  4463.6 1601.90  4619.6 1599.87  4695.4 1600.40  4791.1 1597.60  4934.6 1595.87
  4994.4 1593.82  5008.9 1589.32  5012.0 1587.30  5012.3 1586.80  5016.8 1587.30
  5026.9 1592.40  5057.4 1591.05  5076.8 1593.72  5167.3 1599.21  5179.8 1601.22
  5220.3 1604.26  5229.7 1603.83  5245.3 1606.07  5295.6 1609.60  5364.4 1615.11
#Mann=8,-1,0
  3937.4     0.1       0  3998.9    0.07       0  4024.0     0.1       0
  4167.6    0.07       0  4355.8     0.1       0  5012.0    0.05       0
  5016.8     0.1       0  5295.6    0.07       0
Bank Sta=5012,5016.8
Exp/Cntr=0.3,0.1

Type RM Length L Ch R = 1,3165,444,444,444
BEGIN DESCRIPTION:
Stream0690 6.0
END DESCRIPTION:
XS GIS Cut Line= 3
      1943925.02     13880125.02      1943125.00     13879325.00
      1942975.00     13879325.00
#Sta/Elev= 30
  3873.1 1610.70  3936.0 1608.79  4134.4 1600.21  4161.1 1599.41  4266.9 1597.00
  4332.3 1597.41  4338.7 1596.81  4347.5 1597.52  4374.8 1596.83  4440.8 1597.56
  4445.1 1596.98  4462.0 1597.58  4514.8 1597.30  4525.4 1596.53  4534.2 1597.15
  4669.3 1596.34  4779.9 1594.45  4940.9 1589.22  4962.7 1587.10  4979.3 1586.55
  4983.3 1584.32  4983.7 1583.82  4988.1 1584.32  4992.1 1585.93  4996.6 1589.44
  5004.5 1593.72  5029.5 1597.07  5117.0 1600.23  5123.8 1600.48  5154.5 1601.59
#Mann=7,-1,0
  3873.1     0.1       0  4134.4    0.07       0  4161.1     0.1       0
  4983.3    0.05       0  4988.1     0.1       0  5117.0    0.07       0
  5123.8     0.1       0
Bank Sta=4983.3,4988.1
Exp/Cntr=0.3,0.1

Type RM Length L Ch R = 1,2721,449,449,449
BEGIN DESCRIPTION:
Stream0690 5.0
END DESCRIPTION:
XS GIS Cut Line= 3
      1943925.02     13879775.02      1943375.00     13878975.00
      1942575.01     13879025.00
#Sta/Elev= 30
  4029.1 1598.93  4044.0 1599.43  4069.7 1598.74  4342.1 1590.52  4404.1 1589.84
  4529.9 1586.87  4815.5 1588.25  4902.5 1584.95  4907.1 1584.27  4956.4 1584.90
  4969.3 1583.66  4982.3 1584.18  4992.8 1582.89  4993.2 1582.39  4997.3 1582.39
  4997.6 1582.89  5005.7 1584.14  5018.6 1583.04  5034.4 1584.38  5055.5 1587.37
  5106.6 1591.04  5153.8 1592.29  5300.8 1595.62  5480.6 1600.07  5593.5 1604.57
  5602.5 1605.61  5632.6 1607.09  5656.6 1607.62  5717.5 1613.04  5801.5 1616.11
#Mann=8,-1,0
  4029.1     0.1       0  4342.1    0.07       0  4529.9     0.1       0
  4992.8    0.05       0  4997.6     0.1       0  5153.8   0.035       0
  5300.8    0.07       0  5480.6     0.1       0
Bank Sta=4992.8,4997.6
Exp/Cntr=0.3,0.1

Type RM Length L Ch R = 1,2272,835,835,835
BEGIN DESCRIPTION:
Stream0690 4.0
END DESCRIPTION:
XS GIS Cut Line= 3
      1944025.01     13879225.01      1943725.00     13878725.00
      1943124.97     13878524.99
#Sta/Elev= 30
  4421.3 1592.44  4483.1 1590.40  4495.2 1588.92  4511.1 1584.24  4525.1 1581.61
  4547.7 1579.34  4581.1 1579.19  4749.0 1582.43  4753.3 1581.90  4823.2 1582.31
  4871.3 1580.49  4885.5 1581.51  4904.1 1580.34  4915.1 1580.53  4930.4 1579.06
  4939.1 1580.42  4970.2 1579.91  4986.9 1577.72  4989.1 1574.20  4989.5 1573.70
  4994.0 1574.20  5002.5 1577.99  5021.3 1581.17  5073.5 1587.44  5128.0 1588.37
  5147.2 1589.13  5173.1 1588.43  5248.1 1588.62  5497.9 1589.24  5636.9 1590.15
#Mann=6,-1,0
  4421.3     0.1       0  4989.1    0.05       0  4994.0     0.1       0
  5128.0    0.07       0  5248.1   0.035       0  5497.9    0.07       0
Bank Sta=4989.1,4994
Exp/Cntr=0.3,0.1

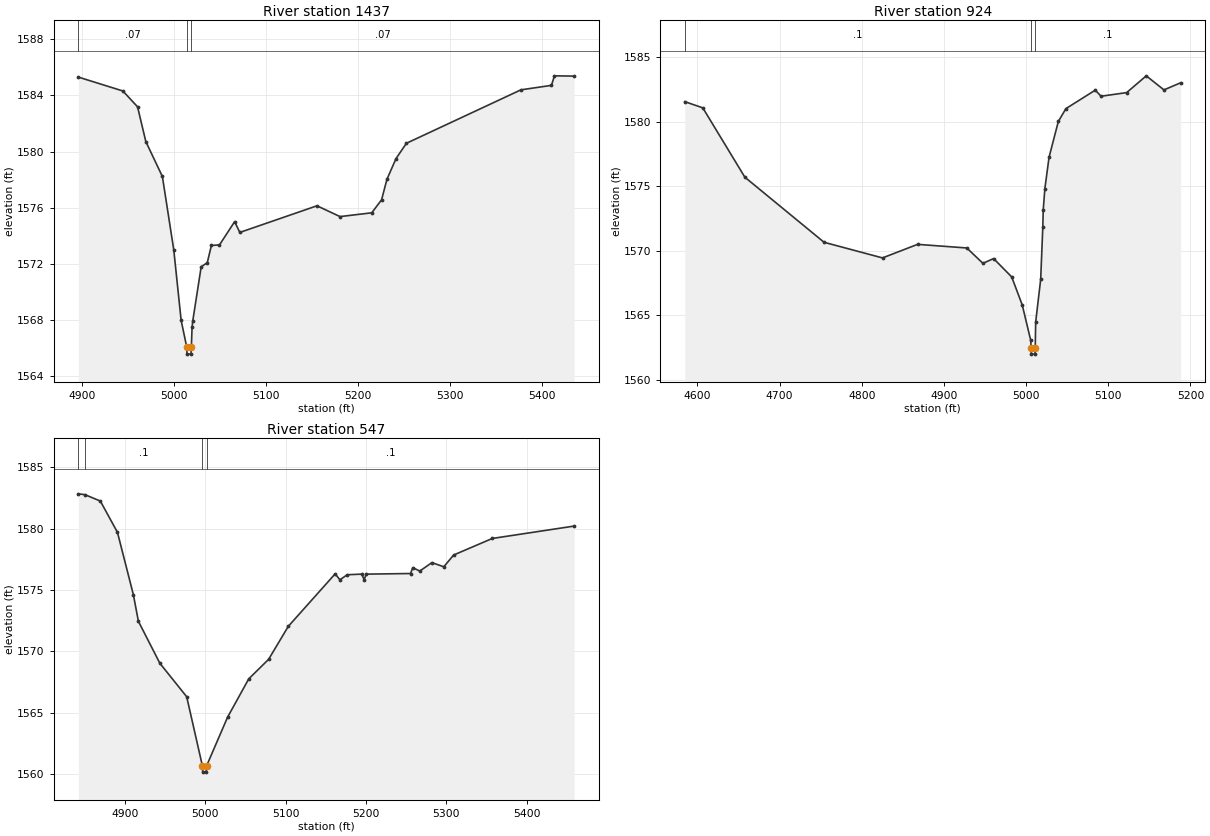
Type RM Length L Ch R = 1,1437,513,513,513
BEGIN DESCRIPTION:
Stream0690 3.0
END DESCRIPTION:
XS GIS Cut Line= 3
      1944425.03     13878625.00      1944325.00     13878625.00
      1943927.18     13878438.96
#Sta/Elev= 30
  4895.7 1585.31  4944.1 1584.32  4960.1 1583.19  4969.1 1580.71  4987.1 1578.22
  4999.5 1572.98  5007.5 1567.96  5013.6 1566.05  5013.9 1565.55  5018.2 1565.55
  5018.6 1566.05  5019.4 1567.48  5020.1 1567.90  5029.3 1571.78  5035.9 1572.07
  5040.4 1573.30  5049.2 1573.34  5065.7 1575.00  5071.3 1574.23  5155.2 1576.13
  5180.3 1575.36  5214.8 1575.63  5225.5 1576.56  5231.3 1578.02  5241.2 1579.50
  5252.5 1580.59  5377.0 1584.40  5410.2 1584.72  5413.5 1585.40  5434.9 1585.38
#Mann=3,-1,0
  4895.7    0.07       0  5013.6    0.05       0  5018.6    0.07       0
Bank Sta=5013.6,5018.6
Exp/Cntr=0.3,0.1

Type RM Length L Ch R = 1,924,377,377,377
BEGIN DESCRIPTION:
Stream0690 2.0
END DESCRIPTION:
XS GIS Cut Line= 3
      1944575.09     13878366.70      1944227.70     13878143.98
      1944040.64     13878106.67
#Sta/Elev= 30
  4584.6 1581.55  4606.5 1581.07  4657.7 1575.70  4754.1 1570.66  4825.2 1569.45
  4867.9 1570.50  4927.8 1570.22  4947.4 1569.03  4960.4 1569.40  4982.4 1567.98
  4995.2 1565.82  5005.5 1563.09  5006.1 1562.50  5006.4 1562.00  5010.7 1562.00
  5011.1 1562.50  5011.6 1564.48  5017.7 1567.79  5020.3 1571.87  5020.8 1573.17
  5022.8 1574.82  5027.9 1577.25  5039.2 1580.02  5048.4 1581.01  5084.1 1582.44
  5091.2 1581.97  5122.3 1582.25  5146.2 1583.55  5167.7 1582.46  5188.0 1583.01
#Mann=3,-1,0
  4584.6     0.1       0  5006.1    0.05       0  5011.1     0.1       0
Bank Sta=5006.1,5011.1
Exp/Cntr=0.3,0.1

Type RM Length L Ch R = 1,547,0,0,0
BEGIN DESCRIPTION:
Stream0690 1.0
END DESCRIPTION:
XS GIS Cut Line= 4
      1944624.99     13878324.98      1944575.00     13878175.00
      1944519.53     13878023.17      1944223.24     13877995.74
#Sta/Elev= 30
  4842.0 1582.84  4850.3 1582.77  4869.4 1582.25  4890.7 1579.70  4910.5 1574.62
  4916.8 1572.44  4943.5 1569.02  4976.9 1566.29  4996.5 1560.64  4996.9 1560.14
  5001.2 1560.14  5001.6 1560.64  5027.8 1564.62  5054.2 1567.75  5078.9 1569.34
  5103.4 1572.03  5161.7 1576.31  5167.7 1575.83  5176.8 1576.24  5194.9 1576.29
  5197.8 1575.84  5200.5 1576.29  5255.6 1576.34  5258.4 1576.82  5267.1 1576.54
  5282.2 1577.23  5297.0 1576.89  5309.3 1577.85  5357.4 1579.20  5459.3 1580.21
#Mann=4,-1,0
  4842.0    0.07       0  4850.3     0.1       0  4996.5    0.05       0
  5001.6     0.1       0
Bank Sta=4996.5,5001.6
Exp/Cntr=0.3,0.1

Chan Stop Cuts=-1