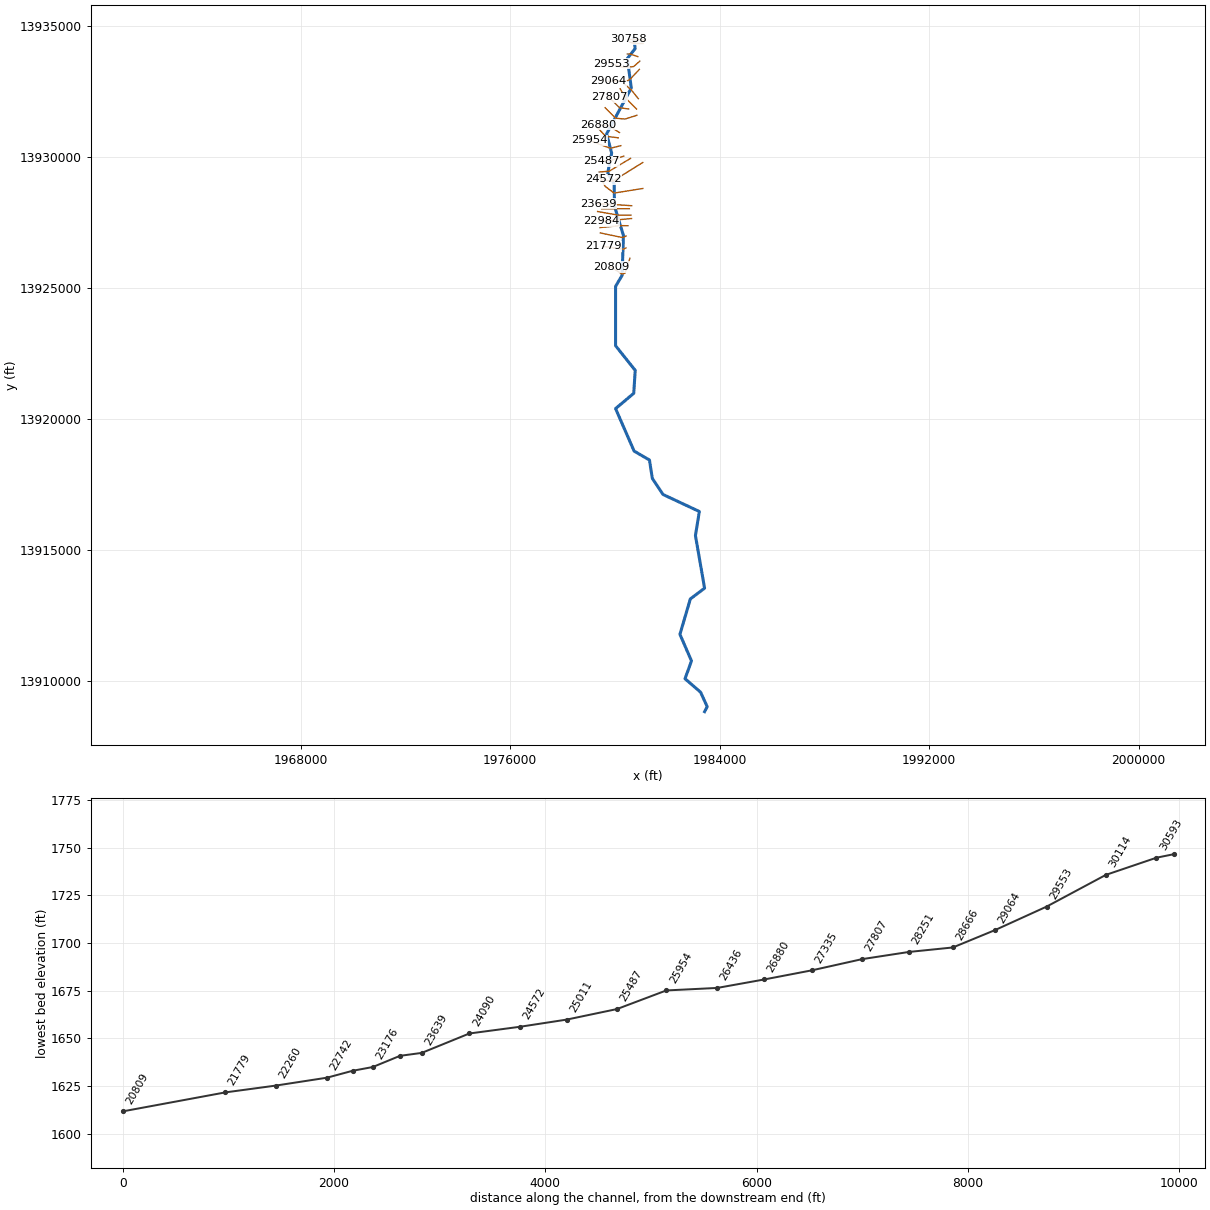
--- Hasenwinkel Creek.prj (project) ---

Proj Title=Hasenwinkel Creek Base Level Engineering
Current Plan=p01
Default Exp/Contr=0.3,0.1
English Units
Geom File=g01
Flow File=f01
Plan File=p01
Y Axis Title=Elevation
X Axis Title(PF)=Main Channel Distance
X Axis Title(XS)=Station
BEGIN DESCRIPTION:
Hasenwinkel Creek
END DESCRIPTION:
DSS Export Rating Curves= 0
DSS Export Rating Curve Sorted= 0
DSS Export Volume Flow Curves= 0
DXF OffsetX= 0
DXF OffsetY= 0
DXF ScaleX= 1
DXF ScaleY= 10

--- Hasenwinkel Creek.p01 (plan) ---

Plan Title=Multiple Run
Short Identifier=Multiple
Geom File=g01
Flow File=f01
Subcritical Flow
K Sum by GR= 0
Std Step Tol= 0.01
Critical Tol= 0.01
Num of Std Step Trials= 20
Max Error Tol= 0.3
Flow Tol Ratio= 0.001
Split Flow NTrial= 30
Split Flow Tol= 0.02
Split Flow Ratio= 0.02
Log Output Level= 0
Friction Slope Method= 1
Unsteady Friction Slope Method= 2
Unsteady Bridges Friction Slope Method= 1
Parabolic Critical Depth
Global Vel Dist=  1 , 1 , 1
Global Log Level= 0
CheckData=True
Encroach Param= -1, 0, 0, 0
BEGIN DESCRIPTION:
Multiple Run
END DESCRIPTION:

--- Hasenwinkel Creek.f01 (steady flow) ---

Flow Title=Multiple
Number of Profiles=7
Profile Names=10-year,25-year,50-year,1pct_min,100-year,1pct_plu,500-year
River Rch & RM= Hasenwinkel Cree,Reach-1,30758
     863    1471    2054    1393    2779    5546    5045
River Rch & RM= Hasenwinkel Cree,Reach-1,28666
    2059    3664    5262    3657    7297   14559   13935
River Rch & RM= Hasenwinkel Cree,Reach-1,20809
    2366    4240    6118    4270    8520   16999   16409
River Rch & RM= Hasenwinkel Cree,Reach-1,20720
    3136    5665    8218    5760   11492   22930   22323
River Rch & RM= Hasenwinkel Cree,Reach-1,12025
    3403    6159    8944    6273   12516   24973   24350
River Rch & RM= Hasenwinkel Cree,Reach-1,7008
    3566    6447    9354    6552   13074   26086   25370
Boundary for River Rch & Prof#=Hasenwinkel Cree,Reach-1,1
Up Type=0
Dn Type=3
Dn Slope=0.005
Boundary for River Rch & Prof#=Hasenwinkel Cree,Reach-1,2
Up Type=0
Dn Type=3
Dn Slope=0.005
Boundary for River Rch & Prof#=Hasenwinkel Cree,Reach-1,3
Up Type=0
Dn Type=3
Dn Slope=0.005
Boundary for River Rch & Prof#=Hasenwinkel Cree,Reach-1,4
Up Type=0
Dn Type=3
Dn Slope=0.005
Boundary for River Rch & Prof#=Hasenwinkel Cree,Reach-1,5
Up Type=0
Dn Type=3
Dn Slope=0.005
Boundary for River Rch & Prof#=Hasenwinkel Cree,Reach-1,6
Up Type=0
Dn Type=3
Dn Slope=0.005
Boundary for River Rch & Prof#=Hasenwinkel Cree,Reach-1,7
Up Type=0
Dn Type=3
Dn Slope=0.005

--- Hasenwinkel Creek.g01 (geometry) ---

Geom Title=Existing Conditions
Program Version=4.10

River Reach=Hasenwinkel Cree,Reach-1
Reach XY= 30
        1980725.       13934525.      1980772.83     13934130.44
      1980474.76     13933750.09        1980625.       13932625.
      1979682.56       13930875.      1979875.36     13930145.15
      1979726.08     13929385.54      1979972.76     13928969.07
      1979982.81     13928121.59      1980325.23     13927000.07
        1980275.       13925475.      1980025.07     13925054.97
      1980025.52     13922790.22      1980775.29     13921850.12
      1980719.17      13920972.7       1980025.5     13920390.22
      1980732.88     13918768.84      1981319.17      13918427.3
      1981428.54     13917726.46      1981838.61     13917111.76
       1983223.4     13916463.19      1983075.07     13915545.03
       1983423.8      13913535.5      1982880.83     13913127.31
      1982482.53     13911774.99      1982924.62     13910759.84
      1982677.05     13910080.86      1983271.49     13909566.52
      1983524.26     13909014.32        1983425.       13908825.

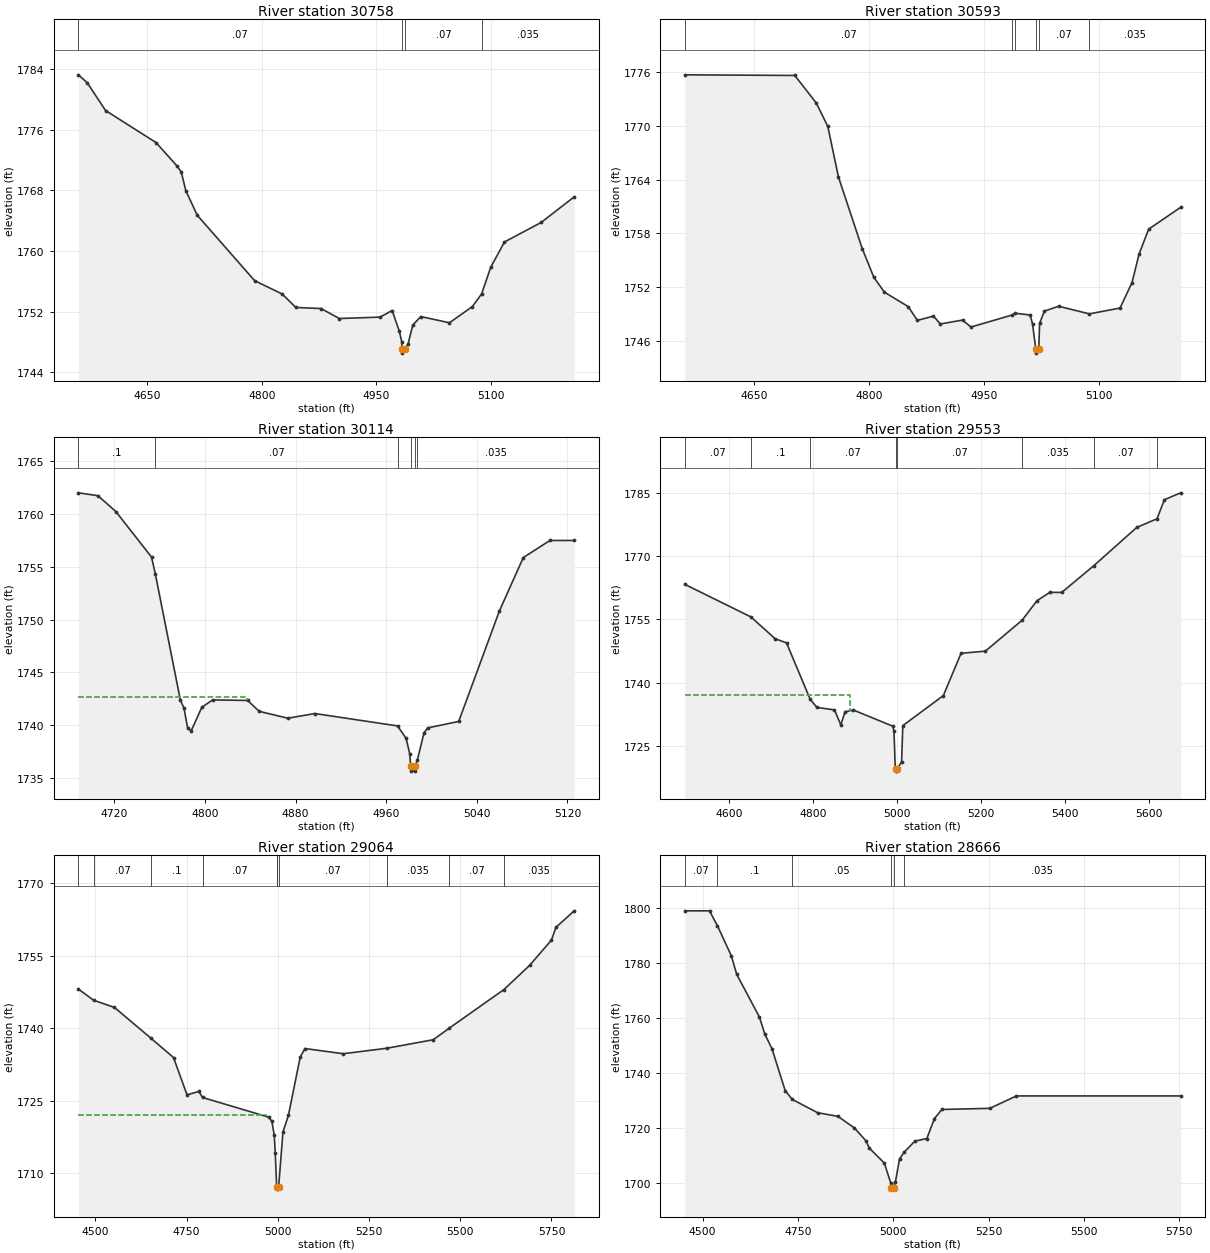
Type RM Length L Ch R = 1 ,30758   ,165,165,165
BEGIN DESCRIPTION:
Hasenwinkel Creek 56.0
END DESCRIPTION:
XS GIS Cut Line= 2
      1981164.18     13934455.95      1980515.34      13934482.9
#Sta/Elev= 30
  4559.8 1783.27  4571.5 1782.22  4595.5 1778.55  4661.5 1774.33  4688.6 1771.28
  4694.6 1770.44  4700.6 1767.96  4715.6 1764.72  4790.7 1756.08  4826.7 1754.32
  4844.7 1752.54  4877.7  1752.4  4901.7 1751.08  4955.1 1751.27  4970.8 1752.14
  4980.2 1749.41  4983.3 1748.03  4983.8 1747.01  4984.1 1746.51  4987.8 1747.01
  4991.8 1747.77  4997.8 1750.21  5008.4 1751.34  5045.9 1750.52  5075.9 1752.66
    5088 1754.33  5099.9 1757.85  5117.9 1761.19    5166 1763.77  5209.2 1767.15
#Mann= 4 ,-1 , 0
  4559.8     .07       0  4983.8     .05       0  4987.8     .07       0
    5088    .035       0
Bank Sta=4983.8,4987.8
XS Rating Curve= 0 ,0
Exp/Cntr=0.3,0.1

Type RM Length L Ch R = 1 ,30593   ,479,479,479
BEGIN DESCRIPTION:
Hasenwinkel Creek 55.0
END DESCRIPTION:
XS GIS Cut Line= 3
        1981075.       13934325.        1980775.       13934325.
      1980574.96     13934375.01
#Sta/Elev= 30
  4559.2 1775.66  4702.8 1775.59  4730.9 1772.52  4745.9 1769.92  4759.8 1764.29
  4790.9  1756.3  4805.9 1753.13  4819.8 1751.45  4850.9 1749.84  4862.9 1748.31
  4883.9 1748.78  4892.9 1747.91  4921.8 1748.34  4932.9 1747.57  4986.81748.911
  4990.8  1749.1  5010.2 1748.91  5013.3 1747.88  5017.4 1745.16  5017.7 1744.66
  5021.4 1745.16  5022.5 1747.98  5028.7 1749.34  5047.3 1749.88  5087.41749.034
  5127.5 1749.68  5143.1 1752.51  5152.4 1755.71  5164.9 1758.47  5206.6  1760.9
#Mann= 6 ,-1 , 0
  4559.2     .07       0  4986.8     .05       0  4990.8     .07       0
  5017.4     .05       0  5021.4     .07       0  5087.4    .035       0
Bank Sta=5017.4,5021.4
XS Rating Curve= 0 ,0
Exp/Cntr=0.3,0.1

Type RM Length L Ch R = 1 ,30114   ,561,561,561
BEGIN DESCRIPTION:
Hasenwinkel Creek 54.0
END DESCRIPTION:
XS GIS Cut Line= 3
      1980875.02     13933824.99        1980575.       13933925.
      1980475.04       13933925.
#Sta/Elev= 30
  4688.3 1761.99  4705.6 1761.72  4721.4 1760.22  4752.9 1755.91  4756.2 1754.34
  4778.4 1742.35  4781.5 1741.63  4784.7 1739.77  4787.8 1739.44  4797.3 1741.69
  4806.8 1742.39  4837.7 1742.34  4847.9 1741.31  4873.2 1740.66  4897.1  1741.1
    49701739.928  4977.6 1738.75  4980.8 1737.29  4981.6 1736.15  4981.8 1735.65
  4985.3 1735.65  4985.6 1736.15  4987.51736.691  4993.4 1739.28  4996.6 1739.74
    5024 1740.35    5060 1750.83    5081 1755.86  5104.5 1757.48  5125.9 1757.48
#Mann= 6 ,-1 , 0
  4688.3      .1       0  4756.2     .07       0    4970     .05       0
  4981.6     .05       0  4985.6     .07       0  4987.5    .035       0
#XS Ineff= 2 , 0
         4836.77 1742.64
Permanent Ineff=
       F       F
Bank Sta=4981.6,4985.6
XS Rating Curve= 0 ,0
Exp/Cntr=0.3,0.1

Type RM Length L Ch R = 1 ,29553   ,489,489,489
BEGIN DESCRIPTION:
Hasenwinkel Creek 53.0
END DESCRIPTION:
XS GIS Cut Line= 4
      1980950.69     13933651.64      1980714.37     13933444.34
      1980330.87      13933409.1      1979870.64       13933548.
#Sta/Elev= 30
  4495.5 1763.34  4652.8 1755.61  4710.6 1750.43  4737.7 1749.44  4793.9 1736.07
  4809.9 1734.13  4851.8 1733.54  4866.9 1729.97  4876.9 1733.11    4897  1733.5
  4990.4 1729.68  4993.4  1728.6  4996.4  1719.8  4997.4 1719.51  4997.7 1719.01
  5001.4 1719.51  5011.5 1721.27  5014.5 1729.81  5110.9 1736.94  5153.1 1746.98
  5210.9 1747.48  5298.6 1754.84  5333.9 1759.47  5364.5 1761.44  5392.7 1761.42
  5469.1 1767.77  5571.3 1776.85  5619.5  1778.9  5637.1 1783.43  5675.7 1785.06
#Mann= 8 ,-1 , 0
  4495.5     .07       0  4652.8      .1       0  4793.9     .07       0
  4997.4     .05       0  5001.4     .07       0  5298.6    .035       0
  5469.1     .07       0  5619.5    .035       0
#XS Ineff= 2 , 0
         4889.69 1737.09
Permanent Ineff=
       F       F
Bank Sta=4997.4,5001.4
XS Rating Curve= 0 ,0
Exp/Cntr=0.3,0.1

Type RM Length L Ch R = 1 ,29064   ,398,398,398
BEGIN DESCRIPTION:
Hasenwinkel Creek 52.0
END DESCRIPTION:
XS GIS Cut Line= 4
      1980934.09     13933336.53      1980594.14     13932973.78
      1980496.71     13932909.52      1979752.54      13932880.5
#Sta/Elev= 30
  4453.6 1748.09  4495.51745.766  4552.5 1744.28  4652.81737.893  4714.4 1733.91
  4751.4 1726.19  4783.8 1726.89  4793.91725.645  4975.3 1721.57    4984 1720.71
  4990.5 1717.78  4993.3 1714.11  4996.9 1707.31  4998.11707.211  4998.5 1707.18
  4998.8 1706.68  5002.5 1707.18  5014.3 1718.51  5029.3 1721.96  5061.6 1734.02
  5074.6 1735.77  5179.7  1734.7  5298.71735.832  5425.9 1737.59  5469.21739.949
  5619.61747.969  5690.1 1752.98  5750.1 1758.22  5762.1 1760.83  5812.2 1764.27
#Mann= 10 ,-1 , 0
  4453.6     .07       0  4495.5     .07       0  4652.8      .1       0
  4793.9     .07       0  4998.1     .05       0  4998.5     .05       0
  5002.5     .07       0  5298.7    .035       0  5469.2     .07       0
  5619.6    .035       0
#XS Ineff= 2 , 0
         4966.89 1721.95
Permanent Ineff=
       F       F
Bank Sta=4998.5,5002.5
XS Rating Curve= 0 ,0
Exp/Cntr=0.3,0.1

Type RM Length L Ch R = 1 ,28666   ,415,415,415
BEGIN DESCRIPTION:
Mapping XS 0ce38f78
END DESCRIPTION:
XS GIS Cut Line= 3
      1980895.78     13932217.85      1980620.15     13932558.59
      1980340.18     13932795.15
#Sta/Elev= 30
  4453.1 1798.83  4517.9 1798.83  4538.71793.396  4575.2 1782.44  4589.2 1775.74
  4648.6 1760.24  4662.9 1754.03  4681.8 1748.61  4716.5 1733.36  4735.11730.219
  4801.2  1725.4  4854.7 1724.06  4897.9 1719.84  4928.7 1715.09  4936.4 1712.58
  4976.2  1707.1  4993.6 1699.65  4994.4  1698.1  4994.9  1697.6  5000.5  1698.1
  5005.4 1700.26  5016.1 1708.54  5028.21711.044  5056.4 1715.06  5087.8    1716
  5107.5 1723.24  5127.1 1726.58  5252.8 1726.98  5322.7  1731.5  5753.2  1731.5
#Mann= 6 ,-1 , 0
  4453.1     .07       0  4538.7      .1       0  4735.1     .05       0
  4994.4     .05       0  5000.5     .07       0  5028.2    .035       0
Bank Sta=4994.4,5000.5
XS Rating Curve= 0 ,0
Exp/Cntr=0.3,0.1

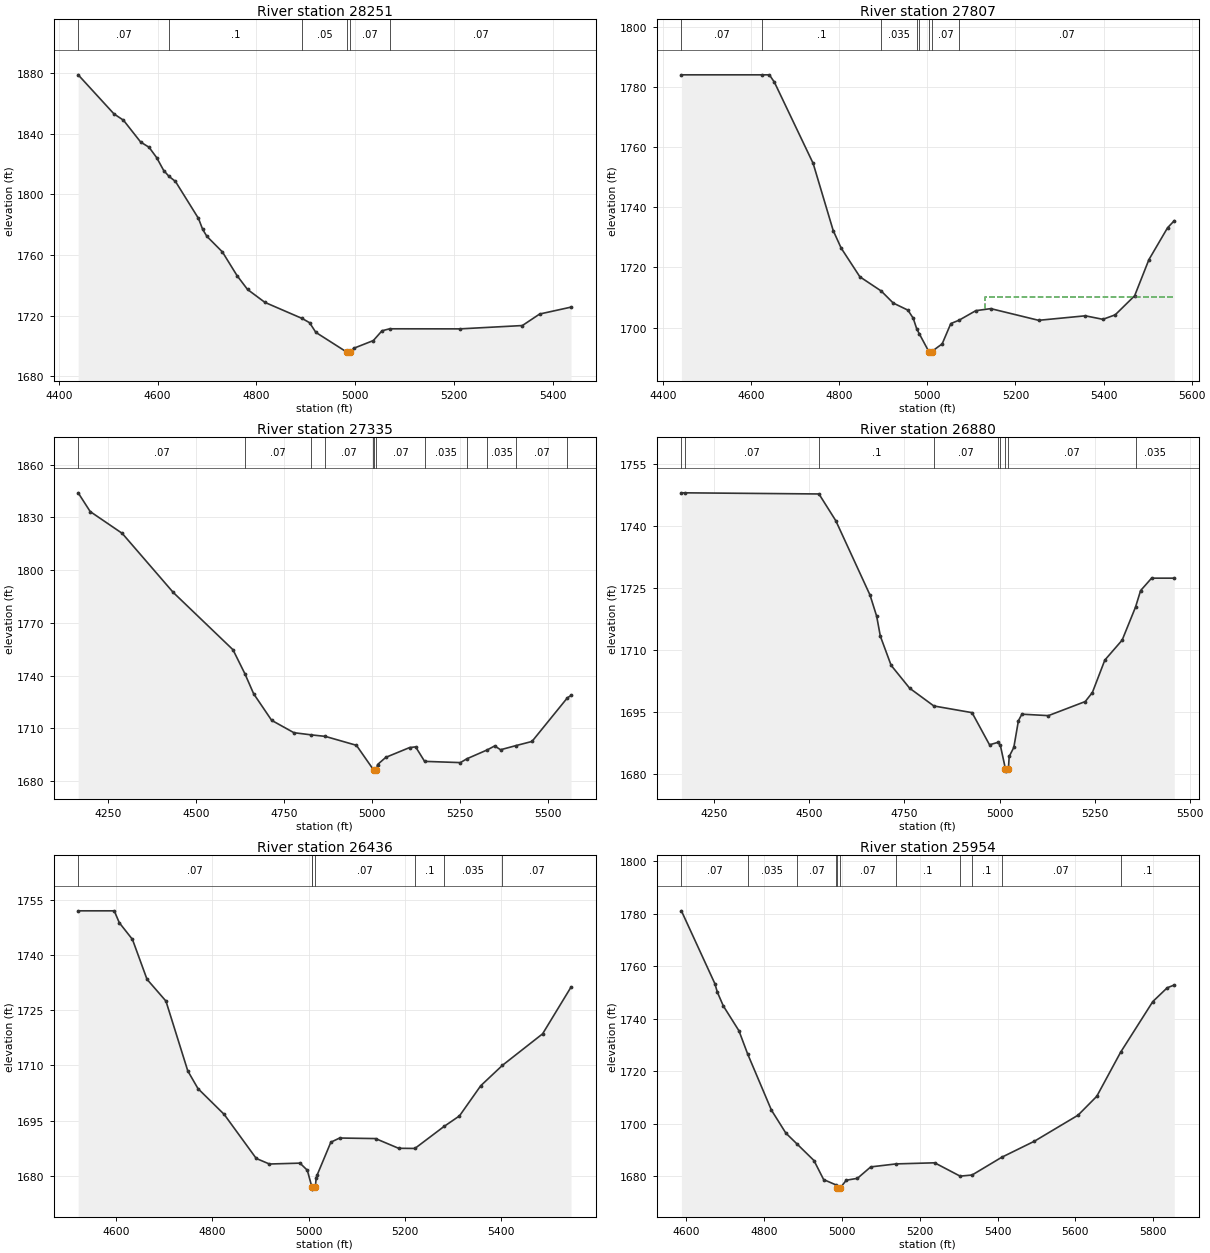
Type RM Length L Ch R = 1 ,28251   ,444,444,444
BEGIN DESCRIPTION:
Hasenwinkel Creek 51.0
END DESCRIPTION:
XS GIS Cut Line= 3
      1980825.02     13931824.98        1980425.       13932225.
      1980200.91     13932594.55
#Sta/Elev= 30
  4439.3 1878.71  4511.9 1852.91    4531 1848.79  4565.8 1834.39  4582.8 1830.96
  4598.1 1824.18  4612.5 1815.61  4623.2 1811.77  4636.3 1808.41  4682.9 1784.01
  4691.4 1776.78  4699.9 1772.24  4731.3 1761.96  4760.9 1746.37  4782.2 1737.22
  4817.4  1728.7  4892.9 1718.08  4907.8  1715.3  4920.5 1708.93    4984 1695.75
  4984.5 1695.25  4990.2 1695.75  4996.9 1698.41  5036.9 1703.53  5054.4 1709.97
  5069.9 1711.29  5212.3 1711.24  5338.6 1713.43  5373.7 1721.03  5437.2 1725.58
#Mann= 6 ,-1 , 0
  4439.3     .07       0  4623.2      .1       0  4892.9     .05       0
    4984     .05       0  4990.2     .07       0  5069.9     .07       0
Bank Sta=4984,4990.2
XS Rating Curve= 0 ,0
Exp/Cntr=0.3,0.1

Type RM Length L Ch R = 1 ,27807   ,472,472,472
BEGIN DESCRIPTION:
Hasenwinkel Creek 50.0
END DESCRIPTION:
XS GIS Cut Line= 3
      1980524.98       13931825.        1980175.       13931875.
      1979775.01     13932274.99
#Sta/Elev= 30
  4441.6  1784.1  4625.5  1784.1  4641.3  1784.1  4652.8 1781.63  4740.7 1754.63
  4786.2 1732.29  4804.3 1726.44  4846.8 1716.88  4895.21712.161  4922.5 1708.15
  4955.9 1705.78  4967.9 1703.09  4975.91699.547  4982.1 1697.81  5003.4 1691.98
  5003.9 1691.48  5009.6 1691.98  5033.6 1694.56  5053.2 1701.31  5072.21702.458
    5110 1705.61  5143.9 1706.29  5252.6  1702.4  5358.6  1703.9  5398.5 1702.73
  5426.5 1704.23  5470.6 1710.58  5502.9 1722.58  5545.3  1733.2  5560.5 1735.55
#Mann= 8 ,-1 , 0
  4441.6     .07       0  4625.5      .1       0  4895.2    .035       0
  4975.9    .035       0  4982.1     .05       0  5003.4     .05       0
  5009.6     .07       0  5072.2     .07       0
#XS Ineff= 2 , 0
                         5131.84         1710.24
Permanent Ineff=
       F       F
Bank Sta=5003.4,5009.6
XS Rating Curve= 0 ,0
Exp/Cntr=0.3,0.1

Type RM Length L Ch R = 1 ,27335   ,455,455,455
BEGIN DESCRIPTION:
Hasenwinkel Creek 49.0
END DESCRIPTION:
XS GIS Cut Line= 4
      1980836.85     13931584.97      1980386.68     13931440.65
        1980025.       13931475.      1979625.02     13931874.98
#Sta/Elev= 30
  4164.6 1843.93  4198.8 1833.27  4289.8 1820.88    4435 1787.26  4604.9 1754.67
  4638.81740.994  4663.6 1729.65  4714.8 1714.53  4778.1  1707.5    48281706.253
  4867.41705.399  4955.9 1700.33  5003.41686.711  5006.3 1686.14  5006.8 1685.64
  5012.7 1686.14    5016 1689.37  5039.4 1693.47  5107.1 1699.04  5124.3 1699.44
  5149.81691.193  5251.6 1690.49    52701692.657  5327.81697.706  5349.1 1699.96
  5365.9  1697.8  5410.11700.183  5455.2 1702.52  5555.91727.341  5566.3 1728.67
#Mann= 12 ,-1 , 0
  4164.6     .07       0  4638.8     .07       0    4828    .035       0
  4867.4     .07       0  5003.4     .05       0  5006.3     .05       0
  5012.7     .07       0  5149.8    .035       0    5270     .07       0
  5327.8    .035       0  5410.1     .07       0  5555.9    .035       0
Bank Sta=5006.3,5012.7
XS Rating Curve= 0 ,0
Exp/Cntr=0.3,0.1

Type RM Length L Ch R = 1 ,26880   ,444,444,444
BEGIN DESCRIPTION:
Hasenwinkel Creek 48.0
END DESCRIPTION:
XS GIS Cut Line= 3
      1980174.97     13930925.02        1979775.       13931175.
      1979374.97       13931225.
#Sta/Elev= 30
  4165.3 1747.96  4175.6 1747.96  4526.21747.686  4570.4 1741.23  4660.2 1723.28
  4677.6 1718.18  4687.2 1713.39  4715.5 1706.34  4764.1 1700.82  4827.61696.532
  4927.8 1694.92  4973.7 1687.16  4995.6 1687.75    50021687.064  5015.5 1681.31
    5016 1680.81  5023.1 1681.31  5025.3 1684.35  5037.4 1686.53  5049.5 1692.99
  5058.6 1694.55  5128.1  1694.2  5224.8  1697.6  5243.5 1699.78  5276.2 1707.61
  5321.6 1712.42  5356.7 1720.39    5370 1724.37  5398.8 1727.37  5458.3 1727.37
#Mann= 9 ,-1 , 0
  4165.3    .035       0  4175.6     .07       0  4526.2      .1       0
  4827.6     .07       0  4995.6     .05       0    5002     .07       0
  5015.5     .05       0  5023.1     .07       0  5356.7    .035       0
Bank Sta=5015.5,5023.1
XS Rating Curve= 0 ,0
Exp/Cntr=0.3,0.1

Type RM Length L Ch R = 1 ,26436   ,482,482,482
BEGIN DESCRIPTION:
Hasenwinkel Creek 47.0
END DESCRIPTION:
XS GIS Cut Line= 4
      1980125.04     13930724.99        1979725.       13930775.
      1979642.46     13930791.28      1979324.99     13931125.01
#Sta/Elev= 30
    4522 1751.96  4596.8 1751.96  4607.3 1748.73  4634.6  1744.2  4664.8 1733.37
  4704.1 1727.45  4749.4 1708.49  4770.6 1703.68    4825 1696.67  4891.5 1684.71
  4918.8  1683.2  4982.2 1683.44  4997.4 1681.52  5006.31677.272  5006.5 1676.88
    5007 1676.38  5014.1 1676.88  5015.7 1679.27  5017.9 1680.22  5046.3 1689.13
  5064.6 1690.26    5139 1690.11  5186.9 1687.47  5220.7 1687.43  5281.21693.403
  5313.2 1696.27  5357.3 1704.46  5402.41710.011  5485.7 1718.56  5544.7 1731.26
#Mann= 7 ,-1 , 0
    4522     .07       0  5006.3     .05       0  5006.5     .05       0
  5014.1     .07       0  5220.7      .1       0  5281.2    .035       0
  5402.4     .07       0
Bank Sta=5006.5,5014.1
XS Rating Curve= 0 ,0
Exp/Cntr=0.3,0.1

Type RM Length L Ch R = 1 ,25954   ,467,467,467
BEGIN DESCRIPTION:
Hasenwinkel Creek 46.0
END DESCRIPTION:
XS GIS Cut Line= 3
      1980225.01       13930425.        1979825.       13930325.
      1979025.02     13930624.99
#Sta/Elev= 30
  4587.5  1781.1  4673.6 1753.33  4679.8 1750.16  4695.2 1744.88  4735.4 1735.41
  4757.7  1726.6  4818.9 1705.17    4856 1696.41  4884.31692.323  4928.3 1685.95
  4953.1  1678.7  4985.71676.612  4988.3 1675.56  4988.8 1675.06  4995.9 1675.56
  5011.3 1678.46  5039.9 1679.17  5074.2 1683.53  5139.2 1684.67  5238.5 1685.09
  5303.91680.011  5334.61680.433  5410.51687.172  5494.9 1693.32    5607 1703.23
  5655.1 1710.42  5716.31727.185  5799.2 1746.53  5836.2 1751.78  5854.3 1752.83
#Mann= 11 ,-1 , 0
  4587.5     .07       0  4757.7    .035       0  4884.3     .07       0
  4985.7     .05       0  4988.3     .05       0  4995.9     .07       0
  5139.2      .1       0  5303.9     .07       0  5334.6      .1       0
  5410.5     .07       0  5716.3      .1       0
Bank Sta=4988.3,4995.9
XS Rating Curve= 0 ,0
Exp/Cntr=0.3,0.1

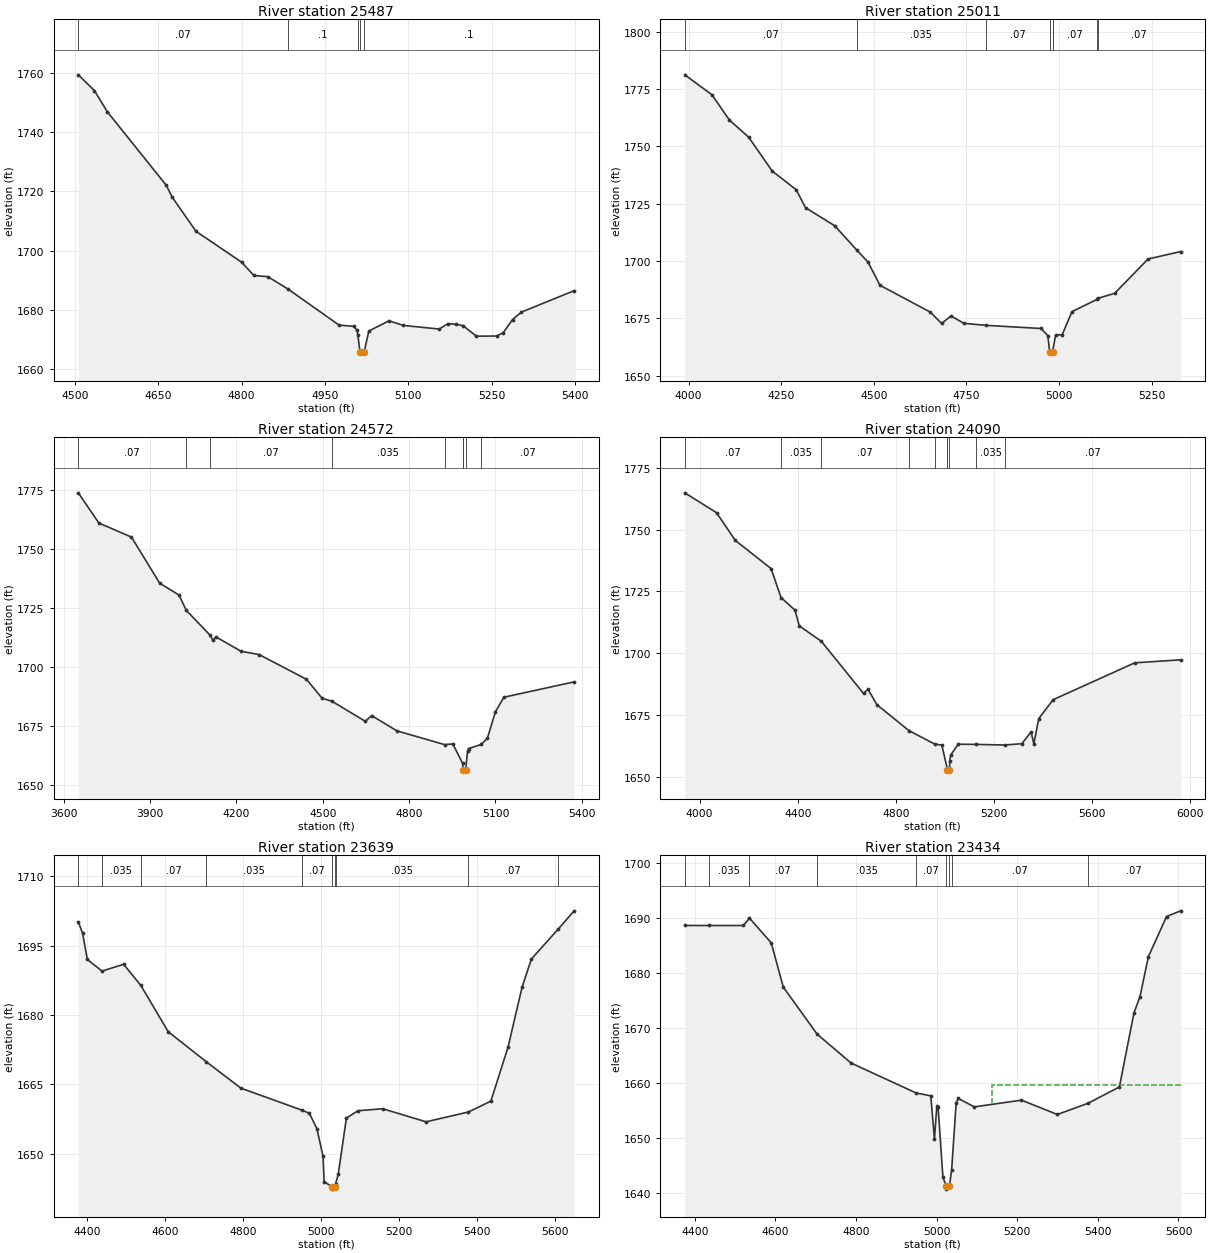
Type RM Length L Ch R = 1 ,25487   ,476,476,476
BEGIN DESCRIPTION:
Hasenwinkel Creek 45.0
END DESCRIPTION:
XS GIS Cut Line= 3
      1980337.92     13930025.56        1979875.       13929875.
        1979475.       13929825.
#Sta/Elev= 30
  4506.2  1759.4  4535.2 1754.05  4558.2 1746.95  4664.3 1722.07  4675.4 1717.93
  4717.9 1706.49  4799.9 1696.06    4822 1691.56  4847.3 1691.14  4883.11687.006
  4975.4 1674.76  5001.6 1674.36  5007.6 1673.03  5009.2 1671.29  5012.8  1665.8
  5013.3  1665.3  5020.5  1665.8  5028.8 1672.77    5065 1676.22  5091.1 1674.66
  5155.6 1673.44  5170.9 1675.25    5186 1675.04  5198.1 1674.62  5222.3 1671.03
  5258.5 1671.09  5270.6  1672.2  5287.3 1676.66  5303.4 1679.17  5398.2 1686.42
#Mann= 5 ,-1 , 0
  4506.2     .07       0  4883.1      .1       0  5009.2     .05       0
  5012.8     .05       0  5020.5      .1       0
Bank Sta=5012.8,5020.5
XS Rating Curve= 0 ,0
Exp/Cntr=0.3,0.1

Type RM Length L Ch R = 1 ,25011   ,439,439,439
BEGIN DESCRIPTION:
Hasenwinkel Creek 44.0
END DESCRIPTION:
XS GIS Cut Line= 3
        1980599.     13929940.76      1979780.75     13929450.83
      1979397.14     13929419.53
#Sta/Elev= 30
  3989.7 1781.27  4062.8 1772.59  4110.3  1761.5  4162.1 1754.06  4225.7 1739.26
  4290.6  1731.1  4315.6 1723.26  4394.4 1715.39  4453.31704.907  4484.5  1699.5
  4516.8 1689.37  4652.6 1677.68  4683.1 1672.71  4708.3 1675.98  4743.2  1672.8
  4801.61671.908  4951.6 1670.53  4969.8 1667.45  4974.9 1660.27  4975.4 1659.77
  4982.7 1660.27  4983.21660.891  4990.8  1667.6  5008.9 1667.89  5035.1  1677.9
  5102.21683.185  5105.31683.695  5150.4  1685.9  5240.7 1700.88  5328.4 1704.11
#Mann= 8 ,-1 , 0
  3989.7     .07       0  4453.3    .035       0  4801.6     .07       0
  4974.9     .05       0  4982.7     .05       0  4983.2     .07       0
  5102.2      .1       0  5105.3     .07       0
Bank Sta=4974.9,4982.7
XS Rating Curve= 0 ,0
Exp/Cntr=0.3,0.1

Type RM Length L Ch R = 1 ,24572   ,482,482,482
BEGIN DESCRIPTION:
Hasenwinkel Creek 43.0
END DESCRIPTION:
XS GIS Cut Line= 4
      1981064.42     13929783.43        1979925.       13929075.
        1979775.       13929075.      1979555.53     13929138.23
#Sta/Elev= 30
  3650.9 1773.66  3722.3  1760.9  3835.6 1754.94  3933.6 1735.45  4001.1 1730.43
  4025.61724.031  4106.71713.738  4118.2 1711.39  4128.8 1712.77  4216.8 1706.67
  4278.6 1705.32  4443.2 1694.87  4497.8 1686.83  4531.61685.592  4648.1 1677.09
  4669.8 1679.52  4757.6 1673.06    4923 1667.26  4951.9 1667.53  4985.71659.406
  4988.3 1656.54  4988.8 1656.04  4996.2 1656.54  5003.4 1664.62  5006.4 1665.57
  5050.31667.302  5072.2 1670.01  5099.4 1680.97  5129.2 1687.27  5373.4 1693.76
#Mann= 9 ,-1 , 0
  3650.9     .07       0  4025.6      .1       0  4106.7     .07       0
  4531.6    .035       0    4923      .1       0  4985.7     .05       0
  4988.3     .05       0  4996.2      .1       0  5050.3     .07       0
Bank Sta=4988.3,4996.2
XS Rating Curve= 0 ,0
Exp/Cntr=0.3,0.1

Type RM Length L Ch R = 1 ,24090   ,451,451,451
BEGIN DESCRIPTION:
Hasenwinkel Creek 42.0
END DESCRIPTION:
XS GIS Cut Line= 4
      1981065.62     13928791.65      1979968.49     13928616.08
        1979625.       13928875.      1979394.62     13929292.86
#Sta/Elev= 30
  3939.8 1764.82  4069.4 1756.78  4145.4 1745.63  4291.4 1734.24    43321722.549
  4388.3  1717.5  4406.6 1711.09  4495.51704.953    4668 1683.87  4686.2 1685.55
  4722.7 1679.29  4853.51668.822  4959.91663.324    4987 1663.06  5009.91653.218
  5010.2 1652.99  5010.7 1652.49  5018.3 1652.99  5019.5 1656.75  5023.4 1659.01
    5054 1663.36  5127.91663.274  5243.41663.034  5313.3 1663.57  5350.8 1668.32
  5362.1 1663.53  5382.1  1673.7    5441 1681.34  5773.4 1696.21  5960.2 1697.42
#Mann= 10 ,-1 , 0
  3939.8     .07       0    4332    .035       0  4495.5     .07       0
  4853.5    .035       0  4959.9     .07       0  5009.9     .05       0
  5010.2     .05       0  5018.3     .07       0  5127.9    .035       0
  5243.4     .07       0
Bank Sta=5010.2,5018.3
XS Rating Curve= 0 ,0
Exp/Cntr=0.3,0.1

Type RM Length L Ch R = 1 ,23639   ,205,205,205
BEGIN DESCRIPTION:
Hasenwinkel Creek 41.0
END DESCRIPTION:
XS GIS Cut Line= 3
      1980641.53     13928133.56        1980025.       13928175.
      1979372.06     13928203.85
#Sta/Elev= 30
  4377.4 1700.12  4388.4 1697.69  4400.4 1692.01  4438.1  1689.5  4493.6 1690.97
  4537.7 1686.39  4607.9 1676.38  4705.6 1669.87  4794.3 1664.16  4951.2 1659.39
  4969.7 1658.73  4989.1 1655.43  5004.8 1649.48  5007.8 1643.95  5027.7 1642.81
  5028.2 1642.31  5035.8 1642.81  5036.9 1643.43  5043.8 1645.48  5064.8 1657.68
  5094.8 1659.28  5157.9 1659.71    5269 1656.88  5377.3 1658.99  5435.3 1661.35
  5479.2 1672.99  5515.3    1686  5539.3 1692.12  5607.6 1698.55  5648.9 1702.54
#Mann= 10 ,-1 , 0
  4377.4     .07       0  4438.1    .035       0  4537.7     .07       0
  4705.6    .035       0  4951.2     .07       0  5027.7     .05       0
  5035.8     .07       0  5036.9    .035       0  5377.3     .07       0
  5607.6    .035       0
Bank Sta=5027.7,5035.8
XS Rating Curve= 0 ,0
Exp/Cntr=0.3,0.1

Type RM Length L Ch R = 1 ,23434   ,258,258,258
BEGIN DESCRIPTION:
Mapping XS a55c1283
END DESCRIPTION:
XS GIS Cut Line= 2
      1980552.63     13928019.38      1979491.43     13928017.84
#Sta/Elev= 30
    4375  1688.6  4435.8  1688.6  4520.4  1688.6  4535.4 1689.94  4589.4 1685.47
  4619.4 1677.42  4703.3  1668.9  4787.4 1663.66  4948.81658.225  4985.4  1657.7
  4994.4 1649.88  5000.4 1655.88  5003.4 1655.75  5015.4 1643.02  5023.4 1641.28
  5023.9 1640.78  5031.5 1641.28  5037.11644.241  5048.4 1656.47  5053.8 1657.22
  5093.4  1655.7  5210.4 1656.92  5299.4 1654.32    53751656.335  5453.4 1659.31
  5489.4 1672.72  5504.4 1675.69  5525.4 1682.96  5570.4 1690.23  5605.3 1691.26
#Mann= 9 ,-1 , 0
    4375     .07       0  4435.8    .035       0  4535.4     .07       0
  4703.3    .035       0  4948.8     .07       0  5023.4     .05       0
  5031.5     .07       0  5037.1     .07       0    5375     .07       0
#XS Ineff= 2 , 0
                         5136.66          1659.7
Permanent Ineff=
       F       F
Bank Sta=5023.4,5031.5
XS Rating Curve= 0 ,0
Exp/Cntr=0.3,0.1

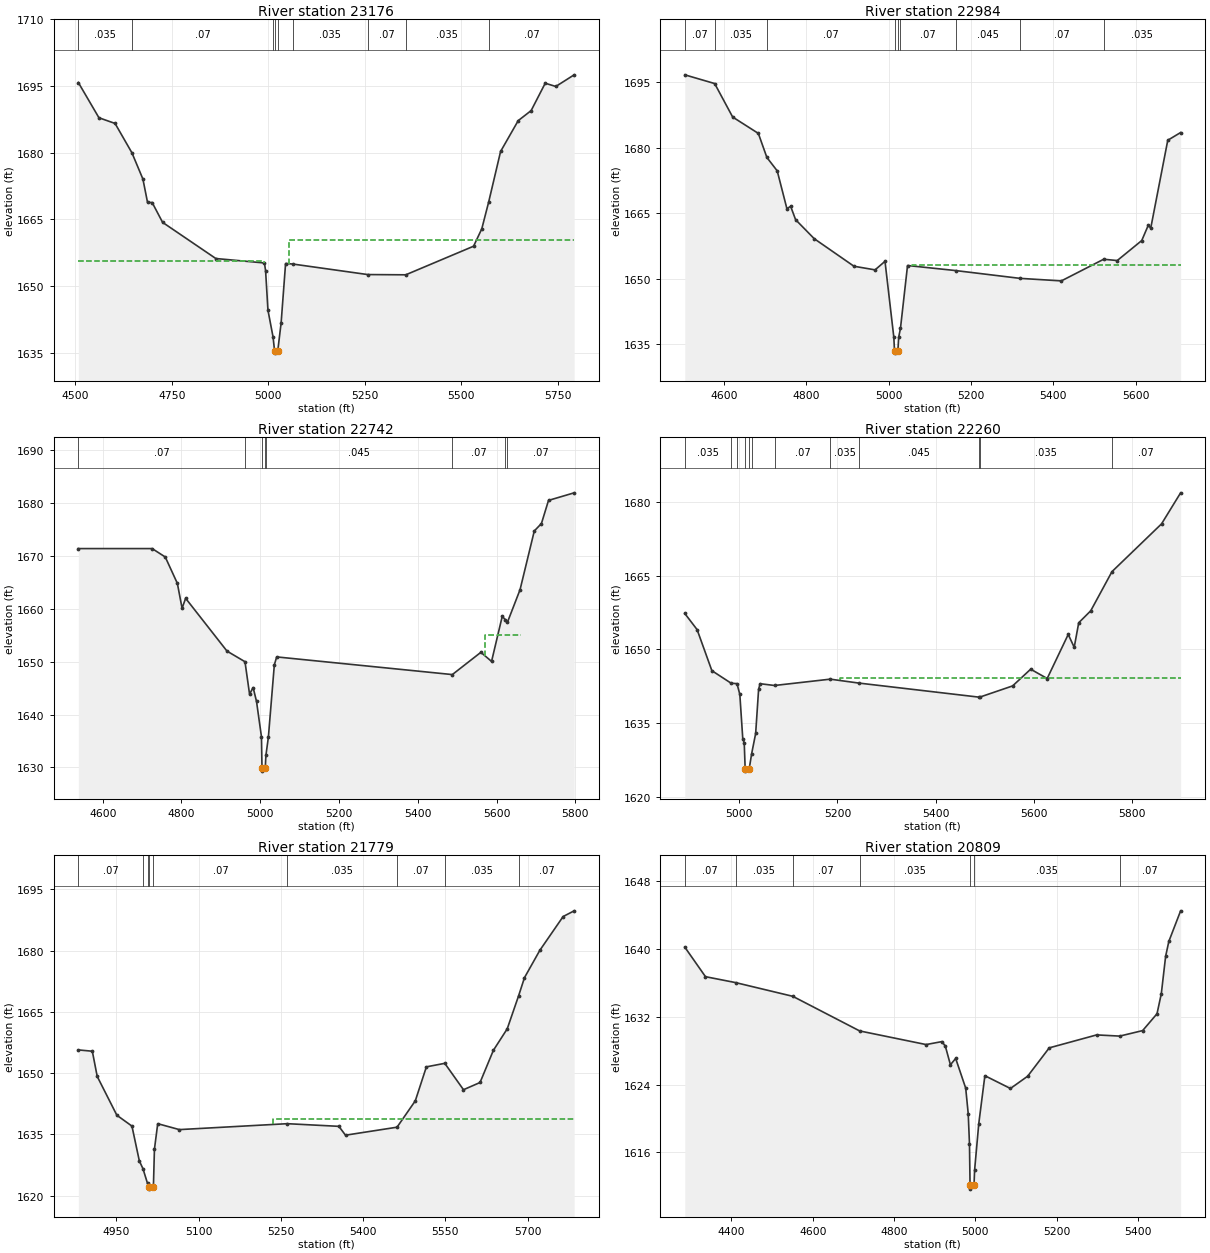
Type RM Length L Ch R = 1 ,23176   ,192,192,192
BEGIN DESCRIPTION:
Hasenwinkel Creek 40.0
END DESCRIPTION:
XS GIS Cut Line= 3
      1980612.02     13927776.23        1980125.       13927775.
      1979338.74      13927912.4
#Sta/Elev= 30
  4507.8 1695.81  4561.2 1687.88    4603  1686.6  4646.71679.995  4675.2 1674.08
  4687.2 1668.82  4699.2  1668.8  4726.2 1664.34  4864.2  1656.2  4990.2  1655.2
  4993.2 1653.43  4999.3 1644.58  5012.51638.557  5016.5 1635.41    5017 1634.91
  5024.7 1635.41  5033.4 1641.67    5045 1655.08  5063.21654.967  5257.9 1652.59
  5356.51652.535  5532.3 1658.97  5553.6 1662.89  5571.61668.983  5602.3 1680.29
    5648 1687.23  5681.5 1689.49    5718 1695.65  5745.4 1694.92    5793 1697.54
#Mann= 9 ,-1 , 0
  4507.8    .035       0  4646.7     .07       0  5012.5     .07       0
  5016.5     .05       0  5024.7     .07       0  5063.2    .035       0
  5257.9     .07       0  5356.5    .035       0  5571.6     .07       0
#XS Ineff= 2 , 0
         4988.31 1655.56 5054.77         1660.43
Permanent Ineff=
       F       F
Bank Sta=5016.5,5024.7
XS Rating Curve= 0 ,0
Exp/Cntr=0.3,0.1

Type RM Length L Ch R = 1 ,22984   ,242,242,242
BEGIN DESCRIPTION:
Mapping XS 442c49da
END DESCRIPTION:
XS GIS Cut Line= 2
      1980634.11     13927645.24      1979469.48     13927532.24
#Sta/Elev= 30
  4505.4 1696.73  4577.91694.729  4621.6 1687.05  4683.9  1683.3  4704.61677.786
  4729.7 1674.71  4753.2 1666.05  4762.3 1666.58  4774.3 1663.52  4819.5 1659.16
    4916 1652.84  4967.2 1652.01  4991.3 1653.97  5012.7 1636.57  5014.4 1633.42
  5014.9 1632.92  5022.6 1633.42  5024.5 1636.55  5028.81638.575    5046 1653.01
  5162.61651.852  5318.41650.068  5419.3 1649.48  5521.91654.442    5555 1654.15
  5614.4 1658.73  5630.3 1662.24  5636.3 1661.59  5677.6 1681.73  5708.8  1683.5
#Mann= 9 ,-1 , 0
  4505.4     .07       0  4577.9    .035       0  4704.6     .07       0
  5014.4     .05       0  5022.6     .07       0  5028.8     .07       0
  5162.6    .045       0  5318.4     .07       0  5521.9    .035       0
#XS Ineff= 2 , 0
                         5056.05         1653.15
Permanent Ineff=
       F       F
Bank Sta=5014.4,5022.6
XS Rating Curve= 0 ,0
Exp/Cntr=0.3,0.1

Type RM Length L Ch R = 1 ,22742   ,482,482,482
BEGIN DESCRIPTION:
Hasenwinkel Creek 39.0
END DESCRIPTION:
XS GIS Cut Line= 3
      1980499.54     13927369.97        1980225.       13927375.
      1979431.82     13927299.04
#Sta/Elev= 30
  4538.1 1671.34  4725.5 1671.34  4758.8 1669.75  4789.5 1664.77  4801.5 1660.07
  4810.5 1661.95  4915.5 1651.98  4961.21649.972  4972.8 1643.86  4981.9 1645.09
  4990.5 1642.46    5003 1635.81  5004.4 1629.81  5004.9 1629.31  5012.6 1629.81
  5014.31632.265  5020.6 1635.73  5035.7 1649.38  5041.7 1650.88  5487.61647.545
  5560.1 1651.75  5587.2 1650.03  5614.3 1658.54    56221657.919  5627.61657.439
  5659.5 1663.57  5695.7 1674.67  5713.8 1676.07  5731.8 1680.44  5796.9 1681.87
#Mann= 8 ,-1 , 0
  4538.1     .07       0  4961.2    .035       0  5004.4    .035       0
  5012.6    .035       0  5014.3    .045       0  5487.6     .07       0
    5622    .035       0  5627.6     .07       0
#XS Ineff= 2 ,-1
 5043.48 5567.561650.714 5570.95 5661.83 1654.94
Permanent Ineff=
       F       F
Bank Sta=5004.4,5012.6
XS Rating Curve= 0 ,0
Exp/Cntr=0.3,0.1

Type RM Length L Ch R = 1 ,22260   ,481,481,481
BEGIN DESCRIPTION:
Hasenwinkel Creek 38.0
END DESCRIPTION:
XS GIS Cut Line= 4
      1980424.99       13926975.        1980325.       13926925.
      1980255.41       13926925.      1979443.19     13927094.49
#Sta/Elev= 30
  4888.7 1657.34  4913.8 1654.05  4943.9 1645.68  4983.31643.113  4995.11643.035
  5000.9 1640.85  5006.9 1631.83  5009.9 1630.97  5011.8 1625.69  5012.3 1625.19
  5020.1 1625.69  5025.11628.785  5033.2 1632.87  5039.2 1641.86  5042.2 1643.02
  5071.71642.657  5185.31643.947  5243.21643.154  5489.4 1640.27  5490.21640.281
  5557.2 1642.57    5594 1645.98  5627.7 1644.08  5670.6 1653.07  5682.8 1650.44
    5692 1655.45  5716.5 1657.89  5759.81665.876  5860.9 1675.62  5899.8 1681.95
#Mann= 12 ,-1 , 0
  4888.7    .035       0  4983.3     .07       0  4995.1    .035       0
  5011.8    .035       0  5020.1    .035       0  5025.1    .035       0
  5071.7     .07       0  5185.3    .035       0  5243.2    .045       0
  5489.4     .07       0  5490.2    .035       0  5759.8     .07       0
#XS Ineff= 2 , 0
                         5204.93         1644.25
Permanent Ineff=
       F       F
Bank Sta=5011.8,5020.1
XS Rating Curve= 0 ,0
Exp/Cntr=0.3,0.1

Type RM Length L Ch R = 1 ,21779   ,970,970,970
BEGIN DESCRIPTION:
Hasenwinkel Creek 37.0
END DESCRIPTION:
XS GIS Cut Line= 3
      1980425.04     13926525.02        1980325.       13926475.
      1979542.69     13926581.73
#Sta/Elev= 30
    4881 1655.69  4906.5 1655.37  4915.4  1649.2  4951.2 1639.69  4978.7 1637.03
  4992.2 1628.49  4998.81626.588  5007.11622.981  5009.5 1622.09    5010 1621.59
  5017.8 1622.09  5019.7 1631.38  5025.7 1637.62  5065.1 1636.17  5261.9 1637.62
  5355.8 1636.97  5367.9  1634.8  5461.8 1636.76  5495.1 1643.22  5515.3 1651.54
  5548.81652.405  5582.9 1645.94  5613.1 1647.71  5637.4 1655.59  5662.6 1660.85
  5683.51669.003  5694.1  1673.4  5722.1  1680.1  5764.5 1688.36  5784.6 1689.76
#Mann= 9 ,-1 , 0
    4881     .07       0  4998.8     .05       0  5007.1     .07       0
  5009.5    .035       0  5017.8     .07       0  5261.9    .035       0
  5461.8     .07       0  5548.8    .035       0  5683.5     .07       0
#XS Ineff= 2 , 0
                         5234.98         1638.74
Permanent Ineff=
       F       F
Bank Sta=5009.5,5017.8
XS Rating Curve= 0 ,0
Exp/Cntr=0.3,0.1

Type RM Length L Ch R = 1 ,20809   ,89,89,89
BEGIN DESCRIPTION:
Hasenwinkel Creek 36.0
END DESCRIPTION:
XS GIS Cut Line= 4
      1980572.11     13926129.02      1980382.33     13925556.67
        1980275.       13925525.      1979846.32     13925792.88
#Sta/Elev= 30
  4285.1 1640.24    4336 1636.75  4410.2 1636.05  4550.9 1634.43  4715.5 1630.34
    4879 1628.73    4918 1629.08  4926.4 1628.54  4938.9 1626.34  4951.8 1627.09
  4976.5 1623.58  4982.7 1620.56  4985.8    1617  4987.2 1612.15  4987.7 1611.65
    4997 1612.15  4998.4 1613.89  5008.7  1619.4  5023.7 1625.05  5086.6 1623.54
    5129 1624.99  5182.1 1628.34  5298.8 1629.87  5355.6 1629.73    5412 1630.38
  5447.4 1632.37    5458 1634.75  5468.6 1639.16  5476.5 1640.92  5505.5 1644.53
#Mann= 7 ,-1 , 0
  4285.1     .07       0  4410.2    .035       0  4550.9     .07       0
  4715.5    .035       0  4987.2    .035       0    4997    .035       0
  5355.6     .07       0
Bank Sta=4987.2,4997
XS Rating Curve= 0 ,0
Exp/Cntr=0.3,0.1