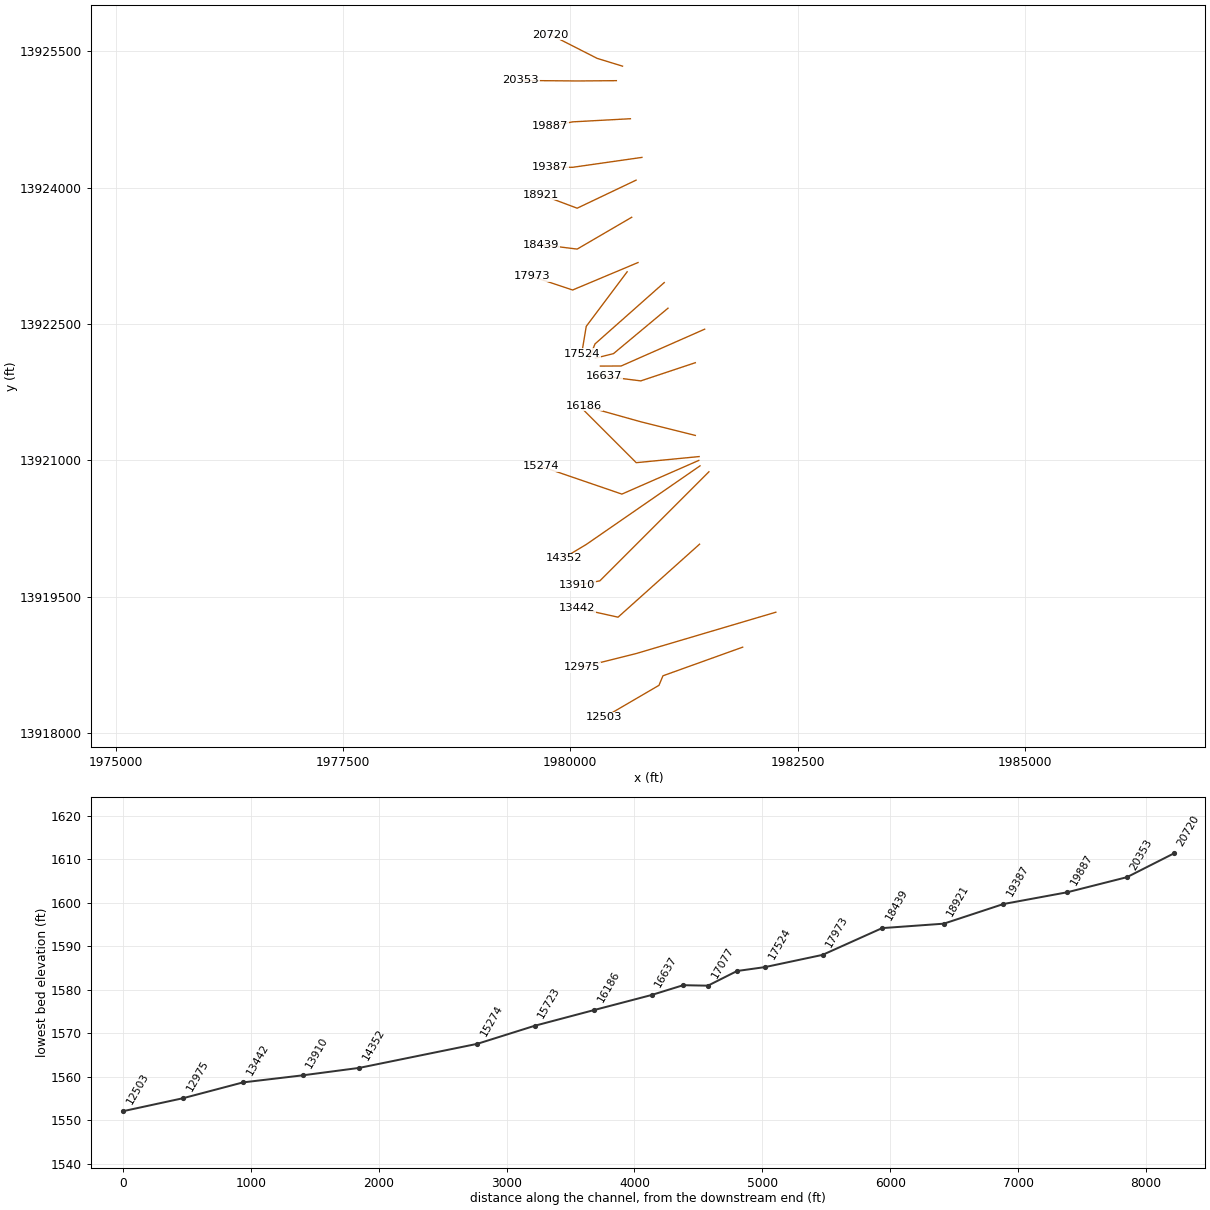
HEC-RAS study Hasenwinkel Creek.prj: Hasenwinkel Creek Base Level Engineering

--- Hasenwinkel Creek.g01 (geometry) --- (continued)

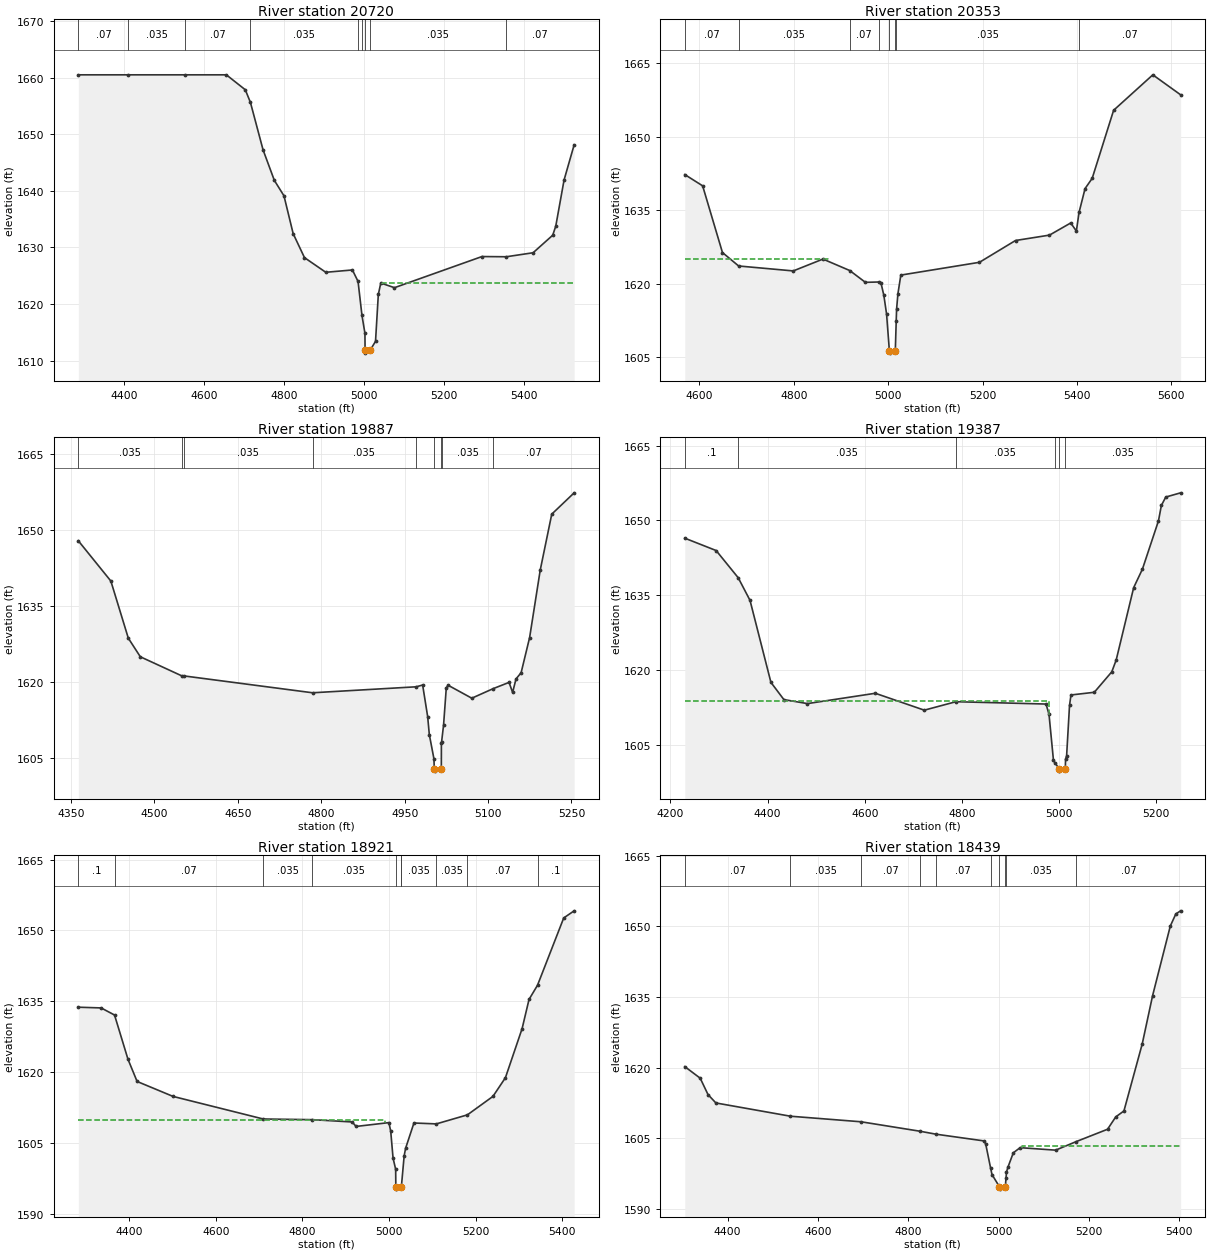
Type RM Length L Ch R = 1 ,20720   ,367,367,367
BEGIN DESCRIPTION:
Mapping XS e5c147be
END DESCRIPTION:
XS GIS Cut Line= 3
      1980574.33     13925337.93       1980294.4     13925423.86
      1979780.08     13925685.58
#Sta/Elev= 30
  4285.1 1660.48  4410.2 1660.48  4550.9 1660.48  4655.3 1660.48  4702.7 1657.84
  4715.51655.613  4747.1 1647.23  4775.3 1641.84  4799.4 1639.11  4822.4 1632.43
  4850.7 1628.19    4904  1625.6  4970.6 1626.01  4984.71623.982  4994.51617.978
  5001.9 1614.83  5002.3 1611.82  5002.8 1611.32  5014.8 1611.82  5028.4  1613.4
  5035.4 1621.68  5041.6  1623.7  5075.8 1622.88  5294.6 1628.38  5355.61628.344
  5422.5 1629.05  5471.6 1632.15  5479.2 1633.75    5500 1641.91  5525.2 1648.12
#Mann= 9 ,-1 , 0
  4285.1     .07       0  4410.2    .035       0  4550.9     .07       0
  4715.5    .035       0  4984.7    .035       0  4994.5    .035       0
  5002.3    .035       0  5014.8    .035       0  5355.6     .07       0
#XS Ineff= 2 , 0
                         5045.53         1623.67
Permanent Ineff=
       F       F
Bank Sta=5002.3,5014.8
XS Rating Curve= 0 ,0
Exp/Cntr=0.3,0.1

Type RM Length L Ch R = 1 ,20353   ,466,466,466
BEGIN DESCRIPTION:
Hasenwinkel Creek 35.0
END DESCRIPTION:
XS GIS Cut Line= 3
      1980506.39     13925178.37        1980075.       13925175.
      1979455.72     13925180.34
#Sta/Elev= 30
    4569 1642.31  4606.8 1640.01  4648.8 1626.39  4683.11623.649  4798.8 1622.64
  4861.8 1625.06  4918.51622.722  4951.7 1620.31  4979.6 1620.38  4984.8 1620.15
  4990.8 1617.66  4996.6 1613.83  5002.5 1606.36    5003 1605.86  5015.1 1606.36
    50171612.335  5017.8 1614.85  5020.7 1618.03  5026.8 1621.79  5193.4  1624.4
  5269.8 1628.85  5341.8 1629.95  5386.8 1632.43  5398.8 1630.78  5404.41634.568
  5417.2 1639.45  5432.3 1641.54  5477.7 1655.43  5560.8 1662.67  5619.7 1658.59
#Mann= 8 ,-1 , 0
    4569     .07       0  4683.1    .035       0  4918.5     .07       0
  4979.6    .035       0  5002.5    .035       0  5015.1    .035       0
    5017    .035       0  5404.4     .07       0
#XS Ineff= 2 , 0
         4872.42 1624.99
Permanent Ineff=
       F       F
Bank Sta=5002.5,5015.1
XS Rating Curve= 0 ,0
Exp/Cntr=0.3,0.1

Type RM Length L Ch R = 1 ,19887   ,500,500,500
BEGIN DESCRIPTION:
Hasenwinkel Creek 34.0
END DESCRIPTION:
XS GIS Cut Line= 3
      1980660.96      13924759.5        1980025.       13924725.
      1979775.04     13924675.01
#Sta/Elev= 30
  4363.1 1647.88  4421.6 1639.93    4453 1628.65  4474.6 1624.98    4549 1621.22
  4552.3 1621.21  4784.4 1617.87  4970.7 1619.05  4982.4  1619.4  4991.4 1613.17
  4994.4 1609.61  5002.7 1604.83  5003.3  1602.9  5003.8  1602.4    5016  1602.9
  5016.1 1607.89  5016.51608.198    5020 1611.47  5024.9 1618.82    5028 1619.37
  5070.8  1616.8  5109.5  1618.7  5137.8 1619.92  5144.2 1617.94  5150.3  1620.6
  5159.5 1621.83  5174.8 1628.78  5193.9 1642.11  5214.6 1653.14  5254.9 1657.35
#Mann= 9 ,-1 , 0
  4363.1    .035       0    4549      .1       0  4552.3    .035       0
  4784.4    .035       0  4970.7    .035       0  5003.3    .035       0
    5016    .035       0  5016.5    .035       0  5109.5     .07       0
Bank Sta=5003.3,5016
XS Rating Curve= 0 ,0
Exp/Cntr=0.3,0.1

Type RM Length L Ch R = 1 ,19387   ,466,466,466
BEGIN DESCRIPTION:
Hasenwinkel Creek 33.0
END DESCRIPTION:
XS GIS Cut Line= 3
      1980787.45      13924333.9        1980025.       13924225.
      1979774.99       13924225.
#Sta/Elev= 30
  4229.8 1646.43  4294.3 1643.95  4339.7 1638.49    4364 1633.95    4407  1617.5
  4433.7 1614.04  4482.2 1613.24  4621.8 1615.31  4722.6 1611.92  4787.7 1613.62
  4973.1 1613.15  4979.2 1611.07  4988.3 1601.92  4991.11601.381  5000.1 1600.19
  5000.6 1599.69  5012.8 1600.19  5013.2 1602.09  5015.4 1602.72  5021.4 1612.87
  5024.4 1614.97  5072.4 1615.51  5108.4 1619.62  5117.4 1621.98  5153.4 1636.51
  5171.4 1640.22  5204.4  1649.9  5210.4    1653  5219.4 1654.68    5250 1655.53
#Mann= 6 ,-1 , 0
  4229.8      .1       0  4339.7    .035       0  4787.7    .035       0
  4991.1    .035       0  5000.1    .035       0  5012.8    .035       0
#XS Ineff= 2 , 0
         4979.44  1613.7 5025.22          1614.9
Permanent Ineff=
       F       F
Bank Sta=5000.1,5012.8
XS Rating Curve= 0 ,0
Exp/Cntr=0.3,0.1

Type RM Length L Ch R = 1 ,18921   ,482,482,482
BEGIN DESCRIPTION:
Hasenwinkel Creek 32.0
END DESCRIPTION:
XS GIS Cut Line= 3
      1980723.11     13924083.57        1980075.       13923775.
      1979675.02     13923924.99
#Sta/Elev= 30
  4282.7 1633.72  4335.3 1633.57  4366.31632.066  4397.4 1622.68  4418.4 1617.99
  4501.5 1614.82  4709.71610.039    48231609.895  4915.1 1609.41  4924.1 1608.46
  4999.9 1609.27  5004.1 1607.45  5009.5 1601.74  5015.5 1599.39  5015.9 1595.68
  5016.4 1595.18  5028.7 1595.68  5028.81595.797  5035.1  1602.2  5038.4 1603.82
  5057.7 1609.19  5109.4    1609  5181.21610.916  5240.2 1614.83    5269 1618.79
  5307.5 1629.19  5323.5 1635.37  5343.1 1638.38  5403.6 1652.63  5427.7 1654.14
#Mann= 10 ,-1 , 0
  4282.7      .1       0  4366.3     .07       0  4709.7    .035       0
    4823    .035       0  5015.9    .035       0  5028.7    .035       0
  5028.8    .035       0  5109.4    .035       0  5181.2     .07       0
  5343.1      .1       0
#XS Ineff= 2 , 0
         4991.03 1609.84
Permanent Ineff=
       F       F
Bank Sta=5015.9,5028.7
XS Rating Curve= 0 ,0
Exp/Cntr=0.3,0.1

Type RM Length L Ch R = 1 ,18439   ,466,466,466
BEGIN DESCRIPTION:
Hasenwinkel Creek 31.0
END DESCRIPTION:
XS GIS Cut Line= 3
        1980675.       13923675.        1980075.       13923325.
      1979675.04       13923375.
#Sta/Elev= 30
  4305.4 1620.19  4339.5 1617.73  4356.8 1614.25  4374.2 1612.47  4539.4 1609.65
  4695.6 1608.47  4826.2 1606.46  4861.41605.834  4968.1  1604.4  4971.6 1603.74
  4982.5 1598.59  4985.5 1597.26    5002 1594.66  5002.5 1594.16    5015 1594.66
  5016.6 1596.58  5017.6 1597.78  5020.6 1598.77  5032.7 1601.88  5047.8 1602.97
  5126.4 1602.44  5172.11604.266  5241.3 1606.88  5259.5 1609.51  5277.6 1610.77
  5318.1 1625.01  5341.1 1635.29  5380.3 1650.07  5392.5 1652.63  5403.1 1653.29
#Mann= 10 ,-1 , 0
  4305.4     .07       0  4539.4    .035       0  4695.6     .07       0
  4826.2    .035       0  4861.4     .07       0  4982.5    .035       0
    5002    .035       0    5015    .035       0  5016.6    .035       0
  5172.1     .07       0
#XS Ineff= 2 , 0
                         5052.24         1603.23
Permanent Ineff=
       F       F
Bank Sta=5002,5015
XS Rating Curve= 0 ,0
Exp/Cntr=0.3,0.1

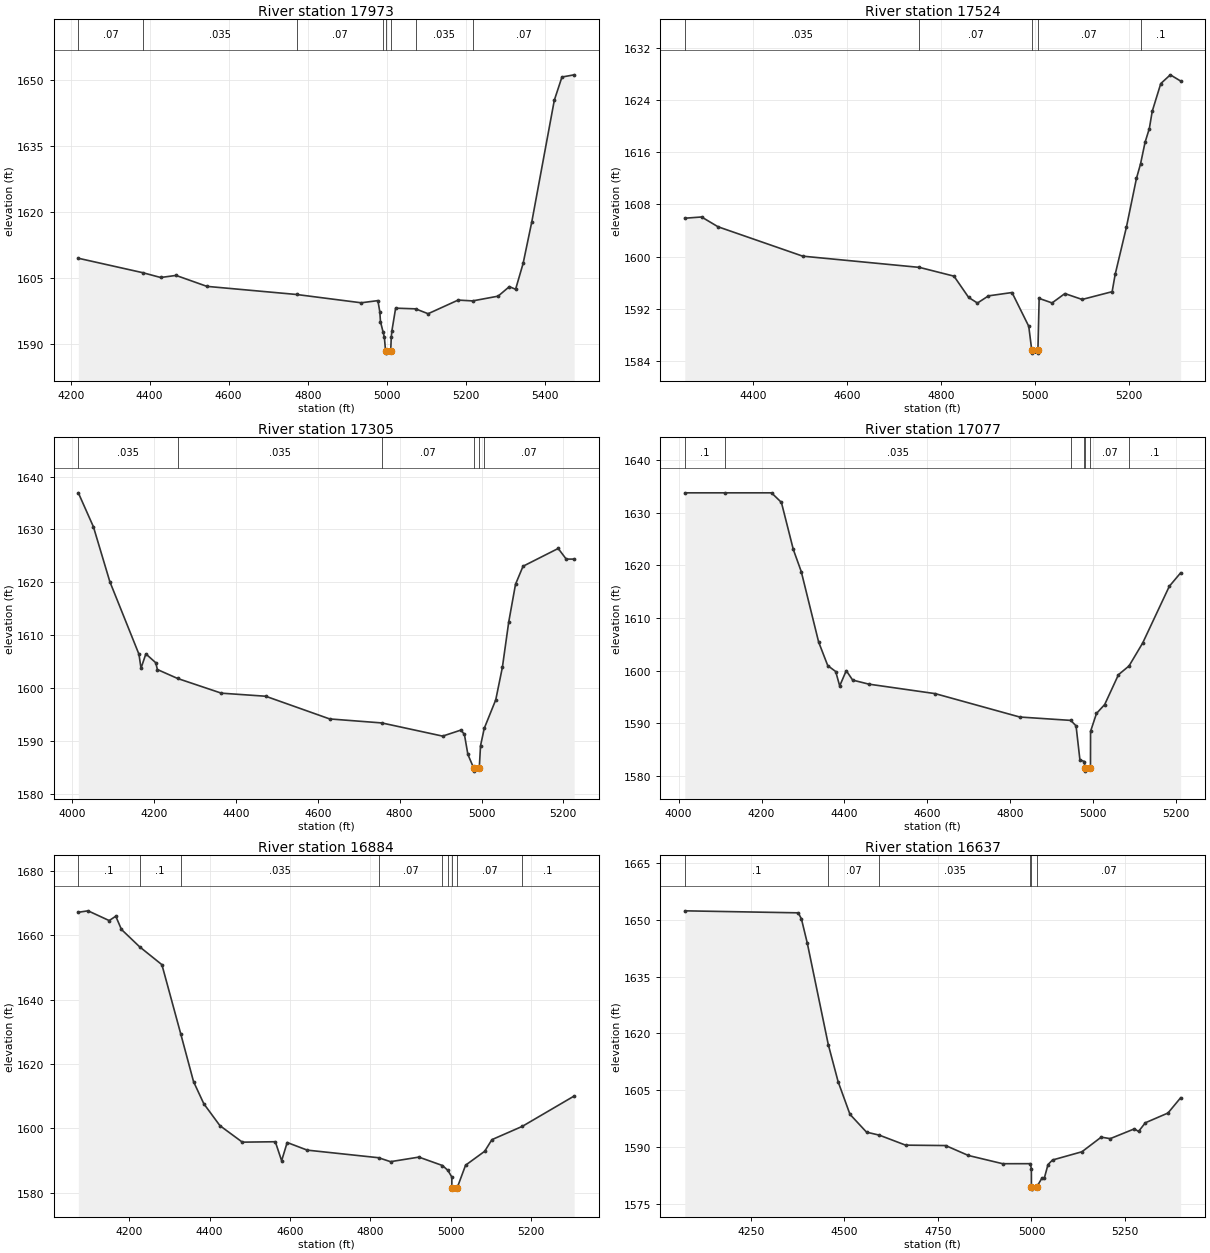
Type RM Length L Ch R = 1 ,17973   ,449,449,449
BEGIN DESCRIPTION:
Hasenwinkel Creek 30.0
END DESCRIPTION:
XS GIS Cut Line= 3
      1980744.45     13923176.88        1980025.       13922875.
      1979574.96     13923025.01
#Sta/Elev= 30
  4219.5 1609.51  4382.5 1606.24  4427.8 1605.15  4466.8 1605.62  4544.9 1603.14
  4771.7  1601.3  4935.3 1599.42  4977.6 1599.91  4982.5 1597.36  4984.1 1595.16
  4990.6 1592.84  4994.1 1591.56    4997 1588.51  4997.5 1588.01    5010 1588.51
  5011.5 1591.68    5013 1593.03  5022.5  1598.2    50731598.045  5104.7 1596.94
  5180.6 1600.03  5217.41599.845  5281.8 1600.92  5310.3 1603.08  5326.1 1602.48
  5345.1 1608.33  5367.2 1617.81  5424.1 1645.33  5443.4 1650.58  5474.3 1651.08
#Mann= 8 ,-1 , 0
  4219.5     .07       0  4382.5    .035       0  4771.7     .07       0
  4990.6     .05       0    4997     .05       0    5010     .07       0
    5073    .035       0  5217.4     .07       0
Bank Sta=4997,5010
XS Rating Curve= 0 ,0
Exp/Cntr=0.3,0.1

Type RM Length L Ch R = 1 ,17524   ,219,219,219
BEGIN DESCRIPTION:
Hasenwinkel Creek 29.0
END DESCRIPTION:
XS GIS Cut Line= 3
      1980625.03     13923075.04        1980175.       13922475.
        1980125.     13922174.99
#Sta/Elev= 30
  4255.2 1605.87  4290.9 1606.06  4325.9 1604.56  4505.9 1600.06  4754.1 1598.34
  4827.5    1597  4858.7 1593.74  4877.4 1592.88  4900.9 1593.98  4950.9 1594.49
  4986.5 1589.32  4992.8 1585.71  4993.3 1585.21  5005.5 1585.21    5006 1585.71
  5008.6 1593.59  5036.1  1592.9  5063.3 1594.33    5100 1593.43  5163.8 1594.62
  5170.2 1597.26  5194.2 1604.52  5215.5 1611.97  5224.2  1614.2  5233.8  1617.5
  5242.9 1619.61    5249 1622.24  5267.2 1626.49  5287.5 1627.83  5309.4 1626.88
#Mann= 5 ,-1 , 0
  4255.2    .035       0  4754.1     .07       0  4992.8     .05       0
    5006     .07       0  5224.2      .1       0
Bank Sta=4992.8,5006
XS Rating Curve= 0 ,0
Exp/Cntr=0.3,0.1

Type RM Length L Ch R = 1 ,17305   ,228,228,228
BEGIN DESCRIPTION:
Mapping XS ae99c8cb
END DESCRIPTION:
XS GIS Cut Line= 3
      1981033.22     13922956.64      1980271.75     13922282.02
      1980204.88     13922120.43
#Sta/Elev= 30
  4014.8 1636.93  4051.7  1630.5  4091.8 1620.13  4162.9 1606.42    4168 1603.76
  4179.8 1606.48    4204  1604.8    4208 1603.52  4257.51601.826  4364.3 1599.05
  4472.6 1598.47  4628.9 1594.18  4756.41593.422    4905 1590.93  4949.7 1592.07
  4958.2 1591.26  4966.7 1587.47  4981.3 1584.81  4981.8 1584.31  4994.5 1584.81
  4997.6 1589.11  5006.81592.419  5034.8 1597.79    5051 1603.93  5066.5  1612.5
  5083.1 1619.64  5101.5 1623.05  5187.4 1626.41    5207  1624.4  5226.4  1624.4
#Mann= 6 ,-1 , 0
  4014.8    .035       0  4257.5    .035       0  4756.4     .07       0
  4981.3     .05       0  4994.5     .05       0  5006.8     .07       0
Bank Sta=4981.3,4994.5
XS Rating Curve= 0 ,0
Exp/Cntr=0.3,0.1

Type RM Length L Ch R = 1 ,17077   ,193,193,193
BEGIN DESCRIPTION:
Hasenwinkel Creek 28.0
END DESCRIPTION:
XS GIS Cut Line= 3
      1981074.96     13922674.97        1980475.       13922175.
      1980275.03     13922125.01
#Sta/Elev= 30
  4014.9 1633.76    4111 1633.76  4224.1 1633.76    4248 1631.94  4276.7 1623.01
  4295.9 1618.81  4337.8 1605.45  4359.8 1600.97    4379 1599.84  4388.6 1597.11
  4404.5 1600.01  4419.9 1598.22  4458.9 1597.45    4619 1595.65    4823 1591.21
  4946.11590.568  4958.9 1589.53  4968.2  1583.1    49791582.754  4980.2 1581.44
  4980.7 1580.94  4993.7 1581.44  4993.9 1588.49  5008.2 1591.89    5028 1593.58
  5061.2 1599.24  5086.71600.902  5119.6 1605.25  5183.9 1616.02  5211.2 1618.57
#Mann= 7 ,-1 , 0
  4014.9      .1       0    4111    .035       0  4946.1     .07       0
    4979     .05       0  4980.2     .05       0  4993.7     .07       0
  5086.7      .1       0
Bank Sta=4980.2,4993.7
XS Rating Curve= 0 ,0
Exp/Cntr=0.3,0.1

Type RM Length L Ch R = 1 ,16884   ,247,247,247
BEGIN DESCRIPTION:
Mapping XS e47caf15
END DESCRIPTION:
XS GIS Cut Line= 3
      1981477.79     13922443.78      1980558.99      13922038.9
      1980330.14     13922037.82
#Sta/Elev= 30
  4073.7 1667.16  4097.9 1667.61  4150.4 1664.58  4166.8 1665.93  4180.9 1661.82
  4226.31656.401  4281.5 1650.86  4328.41629.315  4360.2 1614.48  4385.7 1607.61
  4425.8 1600.79  4481.5 1595.66  4563.5 1595.79  4579.2 1589.88    4593 1595.55
  4642.9 1593.18  4820.31590.815    4850 1589.59  4920.5 1591.01  4979.11588.396
  4992.61586.885  5002.4 1584.82  5002.5 1581.55    5003 1581.05    5016 1581.55
  5036.6 1588.49  5084.1 1592.82  5102.1 1596.44  5177.61600.569  5306.6 1610.01
#Mann= 9 ,-1 , 0
  4073.7      .1       0  4226.3      .1       0  4328.4    .035       0
  4820.3     .07       0  4979.1     .05       0  4992.6     .07       0
  5002.5     .05       0    5016     .07       0  5177.6      .1       0
Bank Sta=5002.5,5016
XS Rating Curve= 0 ,0
Exp/Cntr=0.3,0.1

Type RM Length L Ch R = 1 ,16637   ,451,451,451
BEGIN DESCRIPTION:
Hasenwinkel Creek 27.0
END DESCRIPTION:
XS GIS Cut Line= 3
      1981374.96     13922074.99        1980775.       13921875.
      1980375.03       13921925.
#Sta/Elev= 30
    4074 1652.38    4377 1651.85  4385.5 1650.26  4401.3  1643.8  4457.31617.012
  4483.5 1607.23  4515.2 1598.58  4559.4 1593.87  4593.91593.062  4663.8 1590.43
  4770.8 1590.32  4831.4  1587.7  4923.1 1585.52  4996.91585.529  4999.8  1584.2
  4999.9  1579.3  5000.4  1578.8  5013.5  1579.3  5027.5 1581.61  5034.4 1581.71
  5044.2 1585.29  5056.3  1586.5  5134.9 1588.68  5186.3 1592.54  5210.5 1592.15
  5274.9 1594.73  5286.1 1594.05  5304.2 1596.34  5364.7 1598.92  5398.5 1602.95
#Mann= 6 ,-1 , 0
    4074      .1       0  4457.3     .07       0  4593.9    .035       0
  4996.9     .05       0  4999.9     .05       0  5013.5     .07       0
Bank Sta=4999.9,5013.5
XS Rating Curve= 0 ,0
Exp/Cntr=0.3,0.1

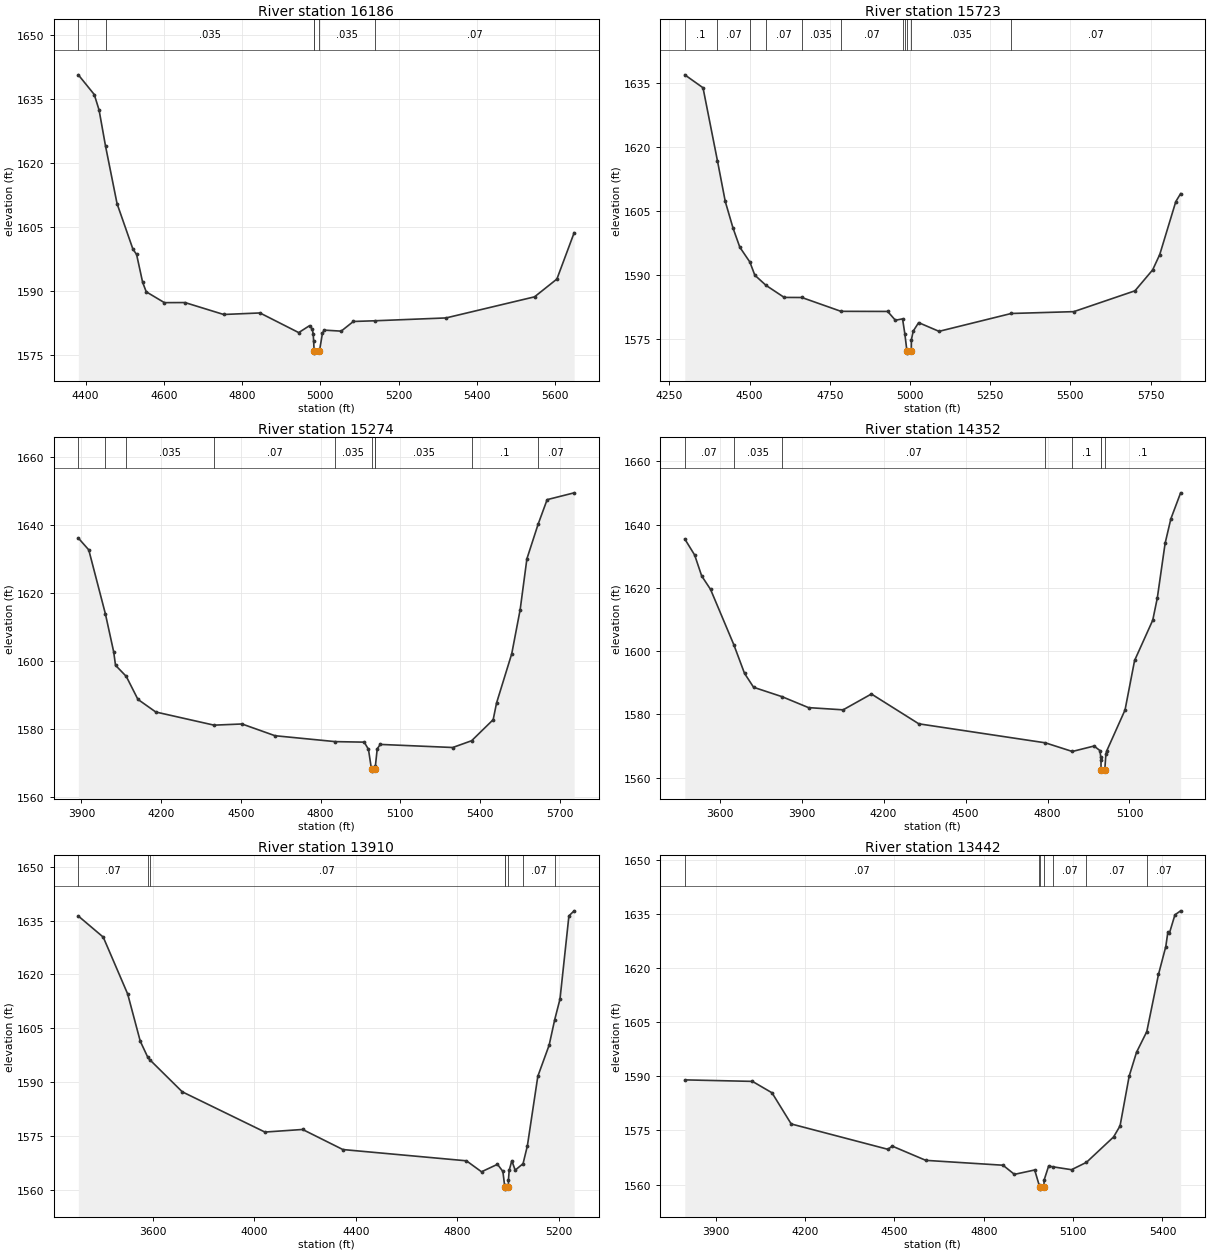
Type RM Length L Ch R = 1 ,16186   ,463,463,463
BEGIN DESCRIPTION:
Hasenwinkel Creek 26.0
END DESCRIPTION:
XS GIS Cut Line= 3
      1981375.05     13921274.99        1980775.       13921425.
      1980150.17     13921600.03
#Sta/Elev= 30
  4381.5 1640.65  4422.2 1636.03  4434.5  1632.4  4451.1 1623.89  4480.5 1610.41
  4521.1 1599.72  4530.4 1598.49  4545.9 1591.94  4555.1 1589.72  4601.5 1587.18
  4654.1  1587.2    4753  1584.4  4845.8 1584.76  4944.8 1580.15  4972.6 1581.78
  4978.8 1581.05  4981.9 1579.92  4982.91578.216  4984.3 1575.83  4984.8 1575.33
  4997.9 1575.83  5005.5 1580.01  5009.8 1580.73  5053.4 1580.49  5084.5 1582.76
  5138.7 1582.92  5321.3 1583.59  5547.6 1588.54  5604.8 1592.72  5648.9 1603.59
#Mann= 6 ,-1 , 0
  4381.5      .1       0  4451.1    .035       0  4982.9    .035       0
  4984.3    .035       0  4997.9    .035       0  5138.7     .07       0
Bank Sta=4984.3,4997.9
XS Rating Curve= 0 ,0
Exp/Cntr=0.3,0.1

Type RM Length L Ch R = 1 ,15723   ,449,449,449
BEGIN DESCRIPTION:
Hasenwinkel Creek 25.0
END DESCRIPTION:
XS GIS Cut Line= 3
      1981417.18     13921042.18        1980725.       13920975.
      1980124.97     13921575.03
#Sta/Elev= 30
  4297.8 1636.88  4354.6 1633.85  4399.71616.717    4424 1607.23  4448.1 1601.02
  4469.4 1596.52  4500.71593.054  4516.1 1589.98    45511587.597  4607.8 1584.77
  4662.71584.753  4784.71581.516  4930.3 1581.49  4954.4 1579.43  4976.81579.748
  4983.91576.265  4990.4 1572.23  4990.9 1571.73    5004 1572.23  5004.4 1574.89
  5009.9 1576.87  5026.9 1578.87  5090.5 1576.83  5315.71581.011  5510.6 1581.44
  5701.5 1586.32  5756.6 1591.22  5778.7 1594.81  5828.8 1607.21  5843.8 1609.07
#Mann= 11 ,-1 , 0
  4297.8      .1       0  4399.7     .07       0  4500.7    .035       0
    4551     .07       0  4662.7    .035       0  4784.7     .07       0
  4976.8    .035       0  4983.9    .035       0  4990.4    .035       0
    5004    .035       0  5315.7     .07       0
Bank Sta=4990.4,5004
XS Rating Curve= 0 ,0
Exp/Cntr=0.3,0.1

Type RM Length L Ch R = 1 ,15274   ,922,922,922
BEGIN DESCRIPTION:
Hasenwinkel Creek 24.1
END DESCRIPTION:
XS GIS Cut Line= 3
      1981413.37     13920999.99      1980567.24     13920629.28
      1979676.37     13920934.55
#Sta/Elev= 30
  3888.5 1636.24  3927.7 1632.77  3990.4 1613.89  4021.6 1602.69  4028.4 1598.77
  4068.91595.482  4112.7 1588.72  4179.9    1585    43991581.126  4504.4 1581.47
  4628.6 1578.01  4855.51576.271  4964.2 1576.12  4980.1 1574.01  4991.6 1568.08
  4992.1 1567.58  5005.2 1568.08  5006.41569.212  5013.1 1574.14  5024.5 1575.45
  5297.2 1574.54  5368.31576.536  5449.4 1582.74  5462.1 1587.65  5519.2 1602.15
  5550.9 1615.13  5576.3 1630.13  5618.31640.281  5652.4 1647.56  5754.1 1649.57
#Mann= 10 ,-1 , 0
  3888.5      .1       0  3990.4     .07       0  4068.9    .035       0
    4399     .07       0  4855.5    .035       0  4991.6    .035       0
  5005.2    .035       0  5006.4    .035       0  5368.3      .1       0
  5618.3     .07       0
Bank Sta=4991.6,5005.2
XS Rating Curve= 0 ,0
Exp/Cntr=0.3,0.1

Type RM Length L Ch R = 1 ,14352   ,442,442,442
BEGIN DESCRIPTION:
Hasenwinkel Creek 24.0
END DESCRIPTION:
XS GIS Cut Line= 3
      1981426.88     13920940.03        1980175.       13920075.
      1979925.02     13919925.01
#Sta/Elev= 30
  3472.2 1635.46  3508.3 1630.39    3534 1623.78  3566.4 1619.53  3651.51602.068
  3690.8 1592.98  3724.1 1588.57  3828.11585.604  3925.2 1582.14  4051.8 1581.44
  4155.3 1586.45  4328.9 1577.02  4791.91571.012  4890.81568.274  4970.5    1570
    4992 1568.55  4994.71566.649  4995.8 1565.57    4996 1562.56  4996.5 1562.06
  5009.8 1562.56  5013.7 1567.43  5017.2 1568.53  5083.8  1581.4  5118.8 1597.05
  5185.2 1609.78  5201.9 1616.78  5230.6 1634.14  5251.6 1641.85  5287.3 1650.06
#Mann= 8 ,-1 , 0
  3472.2     .07       0  3651.5    .035       0  3828.1     .07       0
  4791.9    .035       0  4890.8      .1       0  4994.7     .05       0
    4996    .035       0  5009.8      .1       0
Bank Sta=4996,5009.8
XS Rating Curve= 0 ,0
Exp/Cntr=0.3,0.1

Type RM Length L Ch R = 1 ,13910   ,468,468,468
BEGIN DESCRIPTION:
Hasenwinkel Creek 23.0
END DESCRIPTION:
XS GIS Cut Line= 3
      1981524.97     13920874.97        1980325.       13919675.
      1980074.97     13919624.99
#Sta/Elev= 30
    3308 1636.24  3406.1 1630.38  3502.3 1614.57  3551.8 1601.46  3581.71596.949
  3588.41596.371  3717.2 1587.39  4042.5 1576.21    4191 1576.93  4349.4 1571.35
  4835.9 1568.22  4895.3 1565.17  4958.2 1567.25  4979.4 1565.26  4986.21561.362
  4987.3 1560.85  4987.8 1560.35  5001.2 1560.85  5001.3 1562.87  5004.2 1565.55
  5014.6 1568.25  5027.8 1565.62  5058.81567.422  5075.8 1572.37    5117 1591.72
  5161.5 1600.36  5183.4 1607.43  5204.3 1613.19  5239.4  1636.3    5260 1637.69
#Mann= 8 ,-1 , 0
    3308     .07       0  3581.7    .035       0  3588.4     .07       0
  4986.2    .035       0  4987.3    .035       0  5001.2    .035       0
  5058.8     .07       0  5183.4     .07       0
Bank Sta=4987.3,5001.2
XS Rating Curve= 0 ,0
Exp/Cntr=0.3,0.1

Type RM Length L Ch R = 1 ,13442   ,467,467,467
BEGIN DESCRIPTION:
Hasenwinkel Creek 22.0
END DESCRIPTION:
XS GIS Cut Line= 3
      1981421.71     13920078.18        1980525.       13919275.
        1980075.       13919375.
#Sta/Elev= 30
  3796.2 1588.98  4023.3 1588.56    4089  1585.4  4153.5 1576.77    4478 1569.75
  4492.8 1570.63  4605.4 1566.69  4864.6 1565.34  4902.9 1562.81    4971 1564.02
    49861559.818  4988.2 1559.22  4988.7 1558.72  5002.2 1559.22  5002.5 1561.19
  5017.8  1565.1  5032.2  1564.9  5094.7  1564.1  5144.8 1566.14    5236 1573.18
  5257.6 1576.23  5288.3 1590.03  5312.9 1596.62  5347.4 1602.35  5386.6 1618.17
  5411.2 1625.91  5418.2 1629.92  5423.5 1629.65  5441.9 1634.69    5461  1635.8
#Mann= 7 ,-1 , 0
  3796.2     .07       0    4986    .035       0  4988.2    .035       0
  5002.2    .035       0  5032.2     .07       0  5144.8     .07       0
  5347.4     .07       0
Bank Sta=4988.2,5002.2
XS Rating Curve= 0 ,0
Exp/Cntr=0.3,0.1

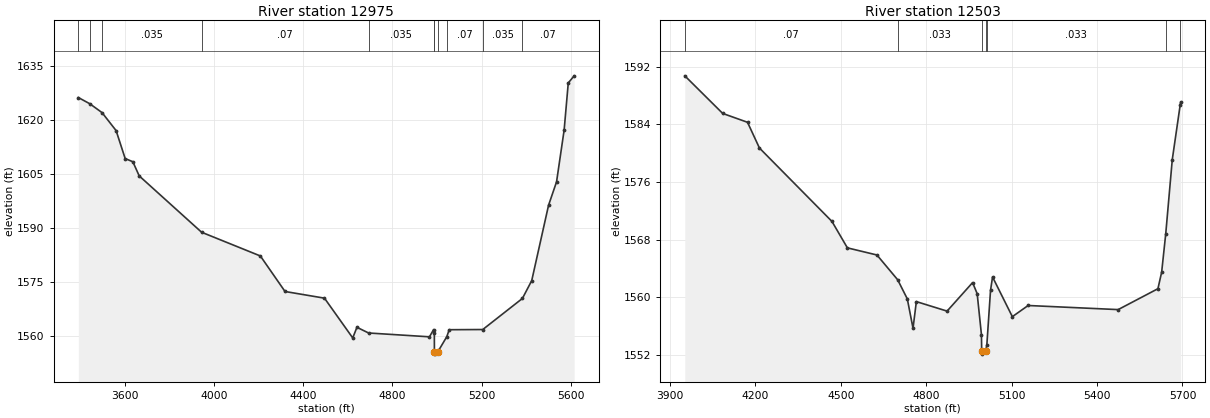
Type RM Length L Ch R = 1 ,12975   ,472,472,472
BEGIN DESCRIPTION:
Hasenwinkel Creek 21.0
END DESCRIPTION:
XS GIS Cut Line= 3
      1982260.99     13919329.66        1980725.       13918875.
      1980125.03     13918725.01
#Sta/Elev= 30
  3391.9 1626.26  3443.41624.533  3498.21622.077  3561.2 1617.09  3601.8 1609.34
  3636.3 1608.45  3664.7 1604.53  3944.41588.902  4207.8 1582.32  4318.3 1572.47
  4495.1 1570.62  4621.8 1559.59  4640.6 1562.54  4692.81560.962  4965.8  1559.9
  4984.21561.909  4987.6 1561.04  4987.8  1555.6  4988.3  1555.1  5001.8  1555.6
  5043.41559.941  5054.2 1561.87  5204.61561.923  5382.21570.538    5424 1575.48
  5499.5  1596.4  5535.3 1602.88  5569.3 1617.23  5587.8 1630.31  5614.2 1632.28
#Mann= 11 ,-1 , 0
  3391.9     .07       0  3443.4      .1       0  3498.2    .035       0
  3944.4     .07       0  4692.8    .035       0  4984.2    .035       0
  4987.8    .035       0  5001.8    .035       0  5043.4     .07       0
  5204.6    .035       0  5382.2     .07       0
Bank Sta=4987.8,5001.8
XS Rating Curve= 0 ,0
Exp/Cntr=0.3,0.1

Type RM Length L Ch R = 1 ,12503   ,478,478,478
BEGIN DESCRIPTION:
Hasenwinkel Creek 20.0
END DESCRIPTION:
XS GIS Cut Line= 4
      1981896.03     13918945.11      1981019.07     13918630.09
        1980975.       13918525.      1980375.09     13918175.05
#Sta/Elev= 30
  3952.2 1590.73  4085.3 1585.51  4172.5 1584.28  4214.3 1580.71    4469 1570.52
  4523.2 1566.85    4627 1565.86  4699.81562.422  4733.6 1559.77  4753.7 1555.69
  4765.4 1559.39  4873.3 1558.07  4962.9 1562.03    4979 1560.49    4994  1554.8
  4994.8  1552.6  4995.3  1552.1  5008.8  1552.6  5012.91553.346  5025.9 1560.95
    5033 1562.81  5102.5  1557.3    5158 1558.85  5474.1 1558.28  5613.8 1561.18
  5626.9 1563.48  5641.31568.833  5664.2 1579.11  5691.91586.669  5693.5 1587.05
#Mann= 7 ,-1 , 0
  3952.2     .07       0  4699.8    .033       0  4994.8    .033       0
  5008.8    .033       0  5012.9    .033       0  5641.3     .07       0
  5691.9      .1       0
Bank Sta=4994.8,5008.8
XS Rating Curve= 0 ,0
Exp/Cntr=0.3,0.1