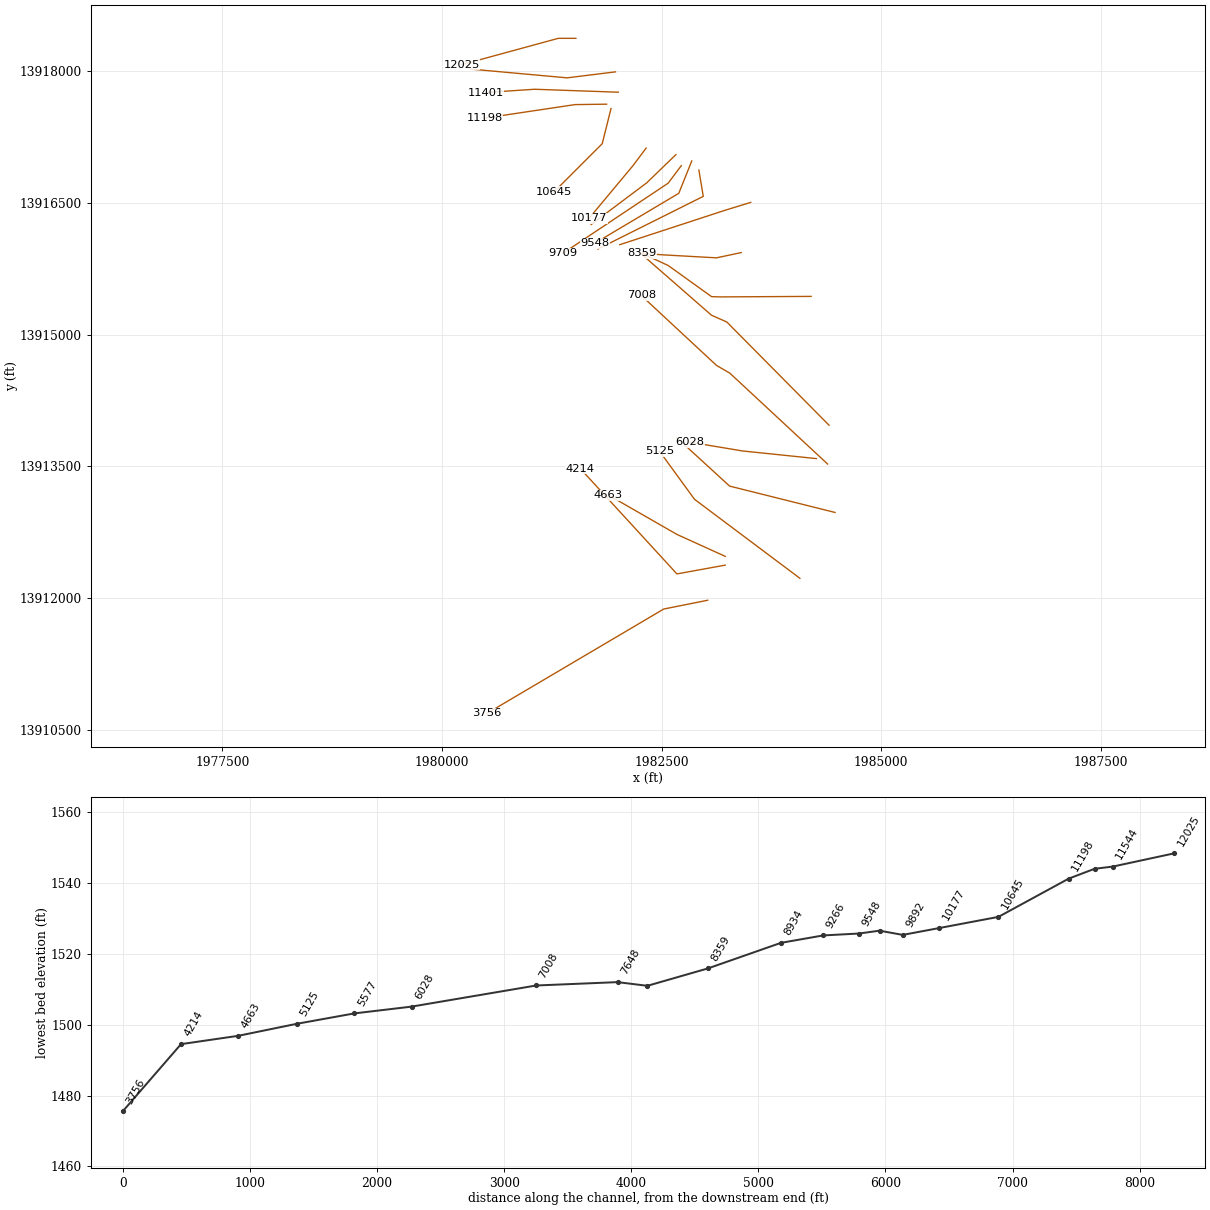
HEC-RAS study Hasenwinkel Creek.prj: Hasenwinkel Creek Base Level Engineering

--- Hasenwinkel Creek.g01 (geometry) --- (continued)

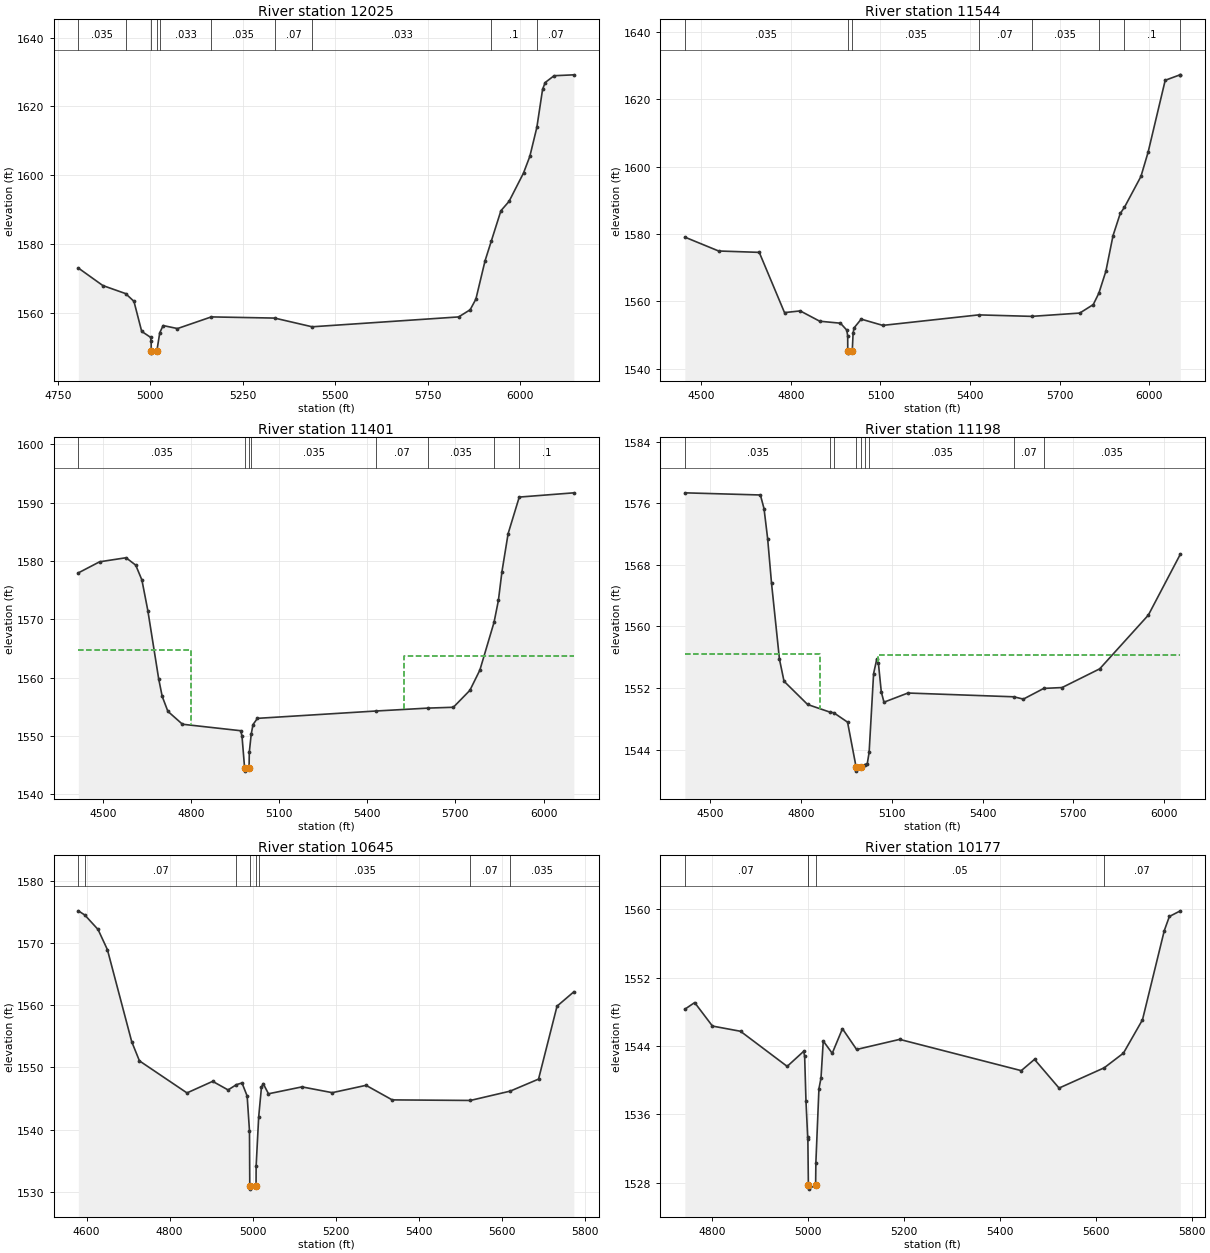
Type RM Length L Ch R = 1 ,12025   ,481,481,481
BEGIN DESCRIPTION:
Hasenwinkel Creek 19.0
END DESCRIPTION:
XS GIS Cut Line= 3
      1981524.98       13918375.        1981325.       13918375.
      1980224.95     13918074.99
#Sta/Elev= 30
  4805.1 1573.06  4871.5 1567.96  4932.9 1565.63  4955.5 1563.39  4976.5 1554.65
  5000.5 1552.92  5002.1 1551.74  5002.3 1548.83  5002.8 1548.33  5017.3 1548.83
  5025.41554.267  5034.5 1556.34  5073.3 1555.47  5164.81558.855  5336.11558.512
  5437.41555.983  5833.7 1558.85  5864.8 1560.93  5880.3 1564.02  5905.2 1575.19
  5921.7 1580.78    5948  1589.7    5970 1592.42  6009.1 1600.65  6026.2  1605.5
  6045.21613.918  6060.7 1624.97  6067.7 1626.95  6091.8 1628.93  6145.3 1629.19
#Mann= 10 ,-1 , 0
  4805.1    .035       0  4932.9    .033       0  5002.3    .033       0
  5017.3    .033       0  5025.4    .033       0  5164.8    .035       0
  5336.1     .07       0  5437.4    .033       0  5921.7      .1       0
  6045.2     .07       0
Bank Sta=5002.3,5017.3
XS Rating Curve= 0 ,0
Exp/Cntr=0.3,0.1

Type RM Length L Ch R = 1 ,11544   ,143,143,143
BEGIN DESCRIPTION:
Hasenwinkel Creek 18.0
END DESCRIPTION:
XS GIS Cut Line= 3
      1981975.98     13917993.24        1981425.       13917925.
      1980325.03       13918025.
#Sta/Elev= 30
  4444.8 1579.07    4558 1574.95  4694.1 1574.54  4778.7 1556.65  4831.3 1557.15
  4896.6 1554.09  4966.1  1553.5  4987.3 1551.44  4990.3 1549.68  4990.5 1545.11
    4991 1544.61  5005.5 1545.11  5008.4 1550.52  5011.4 1552.08  5035.5 1554.71
  5107.8 1552.85    5429 1555.97  5606.8 1555.53  5767.5 1556.51  5812.7 1559.03
  5831.5 1562.42  5854.9  1568.9    5879 1579.53  5903.1 1586.09  5917.3 1587.95
  5972.4 1597.09  5996.5 1604.32  6053.7 1625.66  6103.2 1627.28  6104.5 1627.26
#Mann= 8 ,-1 , 0
  4444.8    .035       0  4990.5    .035       0  5005.5    .035       0
    5429     .07       0  5606.8    .035       0  5831.5    .033       0
  5917.3      .1       0  6103.2     .07       0
Bank Sta=4990.5,5005.5
XS Rating Curve= 0 ,0
Exp/Cntr=0.3,0.1

Type RM Length L Ch R = 1 ,11401   ,203,203,203
BEGIN DESCRIPTION:
Hasenwinkel Creek 17.1
END DESCRIPTION:
XS GIS Cut Line= 3
      1982007.88     13917761.39       1981054.1     13917795.03
      1980499.43     13917757.73
#Sta/Elev= 30
  4416.4 1577.98  4488.7 1579.88  4578.8 1580.58  4611.8 1579.31  4632.8 1576.77
    4653 1571.53  4689.9 1559.83  4701.9 1556.81  4721.3 1554.24  4770.9 1552.03
    4969 1550.92  4973.5 1550.03  4982.5 1544.49    4983 1543.99  4997.6 1544.49
  4998.4 1547.23    50051550.352  5011.1 1551.98  5026.1 1553.04    54291554.297
  5606.91554.798    5693 1554.94  5749.2 1557.84  5783.2 1561.31  5831.51569.511
  5846.3 1573.25  5858.4 1578.19  5879.4 1584.71  5917.31590.981  6103.2 1591.71
#Mann= 8 ,-1 , 0
  4416.4    .035       0  4982.5    .035       0  4997.6    .035       0
    5005    .035       0    5429     .07       0  5606.9    .035       0
  5831.5    .033       0  5917.3      .1       0
#XS Ineff= 2 , 0
          4799.2 1564.75 5525.67         1563.75
Permanent Ineff=
       F       F
Bank Sta=4982.5,4997.6
XS Rating Curve= 0 ,0
Exp/Cntr=0.3,0.1

Type RM Length L Ch R = 1 ,11198   ,553,553,553
BEGIN DESCRIPTION:
Hasenwinkel Creek 17.0
END DESCRIPTION:
XS GIS Cut Line= 3
      1981875.04       13917625.      1981516.13     13917620.36
      1980486.93     13917466.39
#Sta/Elev= 30
    4416 1577.35  4665.8 1577.07  4677.8  1575.3  4689.8 1571.39  4702.6 1565.61
  4728.8 1555.75  4743.9 1552.89  4821.9 1549.87  4897.2 1548.86  4908.2  1548.8
  4953.9 1547.58  4982.3 1541.72  4982.8 1541.22  4997.4 1541.72  5010.11542.064
  5018.9 1542.15  5025.21543.647    5040 1553.89  5050.3 1555.73  5055.8 1555.28
  5065.4 1551.51  5074.3 1550.17  5153.4 1551.36  5503.4 1550.87    5535 1550.57
  5602.6 1551.96    5663 1552.07  5787.4  1554.5  5948.2 1561.48    6054 1569.39
#Mann= 9 ,-1 , 0
    4416    .035       0  4897.2     .07       0  4908.2    .035       0
  4982.3    .035       0  4997.4    .035       0  5010.1    .035       0
  5025.2    .035       0  5503.4     .07       0  5602.6    .035       0
#XS Ineff= 2 , 0
         4862.14 1556.45 5053.95         1556.29
Permanent Ineff=
       F       F
Bank Sta=4982.3,4997.4
XS Rating Curve= 0 ,0
Exp/Cntr=0.3,0.1

Type RM Length L Ch R = 1 ,10645   ,468,468,468
BEGIN DESCRIPTION:
Hasenwinkel Creek 16.0
END DESCRIPTION:
XS GIS Cut Line= 3
      1981925.01     13917575.03        1981825.       13917175.
      1981274.97     13916624.97
#Sta/Elev= 30
  4580.3 1575.14  4595.91574.466  4627.8 1572.14  4650.3  1568.9  4708.8 1554.11
  4727.4 1551.03  4841.8 1545.88  4903.6 1547.74  4940.7 1546.36  4960.81547.211
  4974.2 1547.48  4986.6 1545.38  4992.2 1539.77  4992.9 1530.92  4993.4 1530.42
    5008 1530.92  5008.2 1534.09  5014.31541.991    5021 1546.79  5025.2 1547.38
  5037.9 1545.74  5118.5 1546.85  5191.4 1545.92  5272.7  1547.1  5335.6 1544.76
  5523.8 1544.67  5619.61546.169  5687.8  1548.1  5732.3 1559.82  5772.8 1562.13
#Mann= 8 ,-1 , 0
  4580.3    .035       0  4595.9     .07       0  4960.8    .035       0
  4992.9    .035       0    5008    .035       0  5014.3    .035       0
  5523.8     .07       0  5619.6    .035       0
Bank Sta=4992.9,5008
XS Rating Curve= 0 ,0
Exp/Cntr=0.3,0.1

Type RM Length L Ch R = 1 ,10177   ,285,285,285
BEGIN DESCRIPTION:
Hasenwinkel Creek 15.0
END DESCRIPTION:
XS GIS Cut Line= 3
      1982324.98     13917124.98        1982175.       13916925.
        1981675.       13916325.
#Sta/Elev= 30
  4743.5 1548.31    4764 1549.09  4801.1 1546.34  4859.6 1545.73  4956.9 1541.62
  4991.2 1543.38  4993.3 1542.83  4996.1 1537.53  4999.61533.394    5000 1533.08
  5001.1 1527.75  5001.6 1527.25  5016.2 1527.75  5016.7 1530.35  5023.1    1539
  5027.4 1540.25  5032.1 1544.59  5050.8 1543.15  5072.1 1546.03  5101.6  1543.6
  5191.4 1544.78  5444.9 1541.12  5472.5 1542.44  5523.7 1539.08  5617.81541.452
  5657.9 1543.17  5697.6 1547.07  5743.1 1557.52  5753.7 1559.17  5776.6 1559.83
#Mann= 5 ,-1 , 0
  4743.5     .07       0  4999.6     .07       0  5001.1    .035       0
  5016.2     .05       0  5617.8     .07       0
Bank Sta=5001.1,5016.2
XS Rating Curve= 0 ,0
Exp/Cntr=0.3,0.1

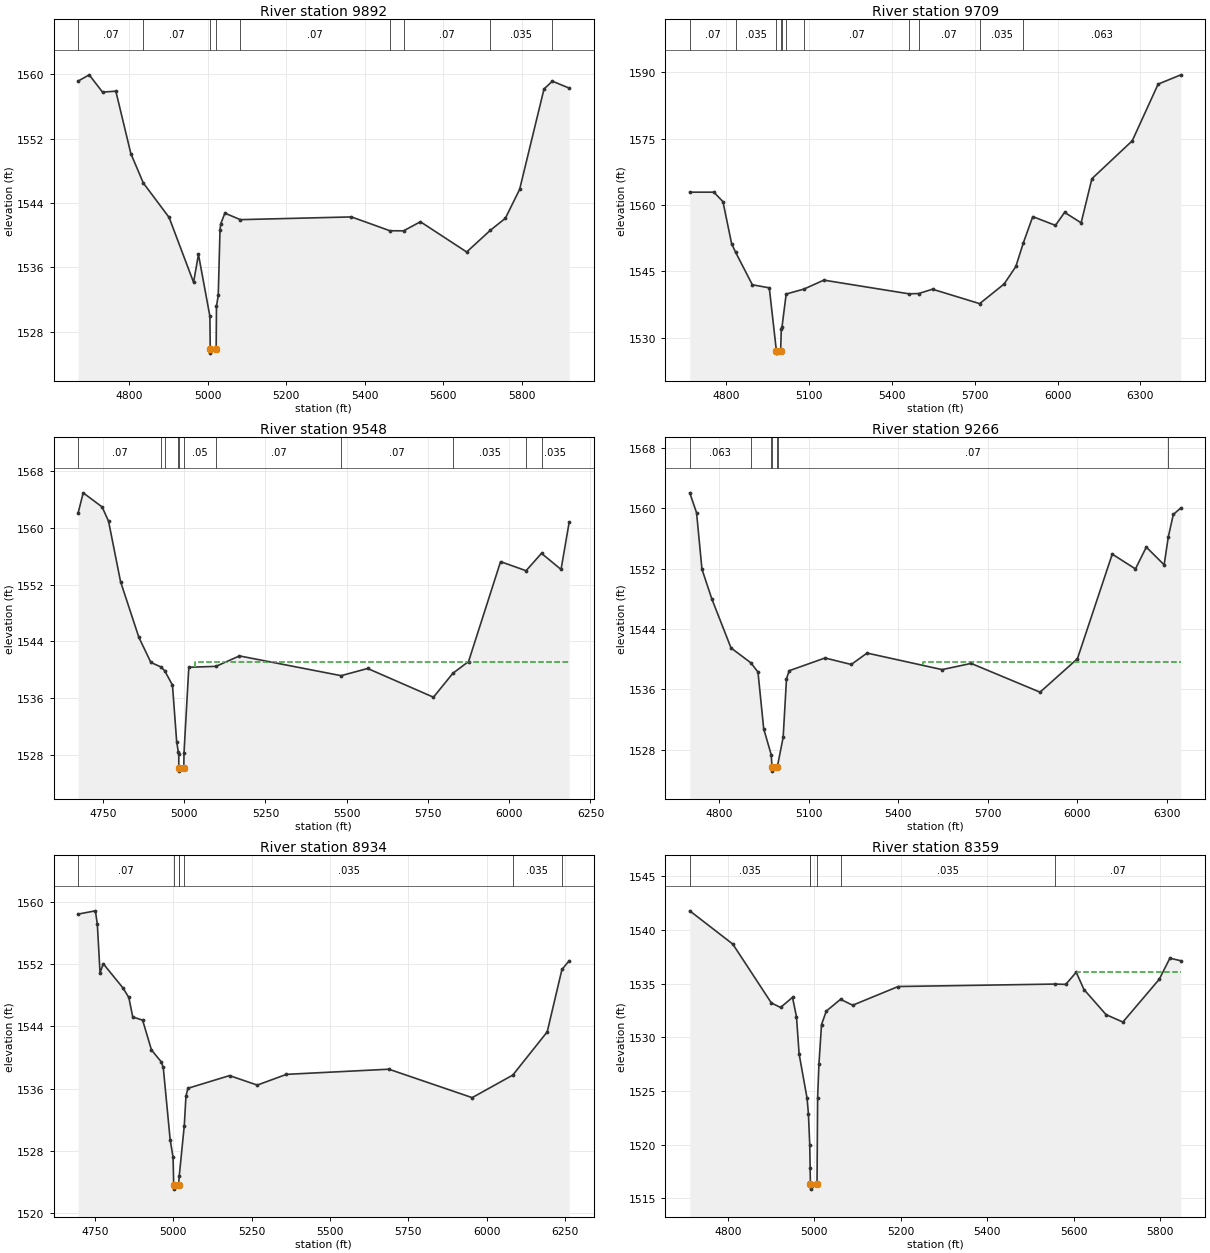
Type RM Length L Ch R = 1 ,9892    ,183,183,183
BEGIN DESCRIPTION:
Mapping XS d6040a15
END DESCRIPTION:
XS GIS Cut Line= 3
      1982663.12      13917050.1      1982331.77     13916729.55
      1981699.39     13916254.93
#Sta/Elev= 30
  4669.3 1559.14  4697.6 1559.92  4731.6 1557.77  4765.5 1557.89  4803.7 1550.14
  4835.5 1546.48  4901.3 1542.19  4963.6 1534.13  4976.1 1537.59  5005.2 1529.91
  5006.1 1525.83  5006.6 1525.33  5021.2 1525.83    5022 1531.16  5026.5  1532.5
    5031 1540.63  5032.8 1541.39  5043.4 1542.73  5082.8 1541.92  5366.1 1542.26
    5464 1540.54  5498.9 1540.53  5541.8 1541.66  5659.7  1537.9  5719.8 1540.59
  5758.3 1542.09  5794.7 1545.69  5856.8 1558.16  5878.1 1559.13    5921 1558.27
#Mann= 9 ,-1 , 0
  4669.3     .07       0  4835.5     .07       0  5006.1    .035       0
  5021.2     .07       0  5082.8     .07       0    5464    .035       0
  5498.9     .07       0  5719.8    .035       0  5878.1    .063       0
Bank Sta=5006.1,5021.2
XS Rating Curve= 0 ,0
Exp/Cntr=0.3,0.1

Type RM Length L Ch R = 1 ,9709    ,161,161,161
BEGIN DESCRIPTION:
Hasenwinkel Creek 14.0
END DESCRIPTION:
XS GIS Cut Line= 3
      1982725.02     13916925.02        1982575.       13916725.
      1981375.04     13915925.03
#Sta/Elev= 30
  4667.2 1562.88  4754.7 1562.88  4787.5 1560.73    4819 1551.22  4833.5 1549.29
    4894 1541.96  4955.4 1541.27  4981.2 1527.02  4981.7 1526.52  4996.5 1527.02
    4999 1531.88  5001.51532.427  5016.61539.873  5080.81540.984    5153 1543.01
  5461.91539.916  5496.91539.984  5546.9 1540.96  5717.81537.699  5806.5 1542.14
  5848.9 1546.09  5876.11551.435  5910.2 1557.36  5992.5 1555.38  6025.6 1558.32
  6085.5 1555.96  6124.5 1565.92  6270.8 1574.49  6364.5 1587.29  6446.9 1589.39
#Mann= 11 ,-1 , 0
  4667.2     .07       0  4833.5    .035       0  4981.2    .035       0
  4996.5    .035       0  5001.5    .035       0  5016.6    .035       0
  5080.8     .07       0  5461.9    .035       0  5496.9     .07       0
  5717.8    .035       0  5876.1    .063       0
Bank Sta=4981.2,4996.5
XS Rating Curve= 0 ,0
Exp/Cntr=0.3,0.1

Type RM Length L Ch R = 1 ,9548    ,282,282,282
BEGIN DESCRIPTION:
Mapping XS 74709328
END DESCRIPTION:
XS GIS Cut Line= 3
      1982843.83     13916978.19      1982696.44      13916609.9
      1981738.57     13916040.14
#Sta/Elev= 30
  4673.4 1562.09  4689.1 1564.95  4747.3 1562.96  4767.1 1560.95    4804 1552.44
  4860.4 1544.58  4897.4 1541.04  4927.5 1540.42  4939.4  1539.9  4963.8 1537.85
  4976.7 1529.89  4981.61528.479  4983.2 1528.17  4983.3 1526.22  4983.8 1525.72
  4998.6 1526.22  4999.3 1528.29  5014.1 1540.36  5097.6 1540.49    5170 1541.96
  5482.81539.175  5564.4 1540.19  5766.9 1536.14  5826.6 1539.51  5874.9 1541.17
  5973.4 1555.25  6051.9 1553.97  6099.4 1556.42  6159.5 1554.15  6184.6 1560.83
#Mann= 11 ,-1 , 0
  4673.4     .07       0  4927.5    .035       0  4939.4     .07       0
  4981.6     .07       0  4983.3    .035       0  4998.6     .05       0
  5097.6     .07       0  5482.8     .07       0  5826.6    .035       0
  6051.9    .063       0  6099.4    .035       0
#XS Ineff= 2 , 0
                         5034.08         1541.13
Permanent Ineff=
       F       F
Bank Sta=4983.3,4998.6
XS Rating Curve= 0 ,0
Exp/Cntr=0.3,0.1

Type RM Length L Ch R = 1 ,9266    ,332,332,332
BEGIN DESCRIPTION:
Hasenwinkel Creek 13.0
END DESCRIPTION:
XS GIS Cut Line= 3
      1982924.99     13916875.03        1982975.       13916575.
      1981775.01       13915975.
#Sta/Elev= 30
  4701.4 1562.05  4724.2 1559.41  4742.3 1551.93  4775.4 1547.99  4839.7  1541.5
  4906.11539.533    4930 1538.31  4949.2 1530.79  4974.41527.352  4977.1 1525.68
  4977.6 1525.18  4992.4 1525.68  4995.6 1525.89  5014.4 1529.66  5025.6  1537.4
  5034.5 1538.48  5154.7 1540.17  5242.5 1539.31  5295.6 1540.82  5547.1 1538.63
  5644.4 1539.45  5875.3 1535.64  6000.5 1540.07  6117.3 1553.93    6195 1551.97
  6231.4 1554.86  6291.2 1552.51  6305.11556.215  6321.9 1559.18  6347.2 1560.05
#Mann= 7 ,-1 , 0
  4701.4    .063       0  4906.1    .035       0  4974.4     .07       0
  4977.1     .05       0  4992.4     .05       0  4995.6     .07       0
  6305.1    .035       0
#XS Ineff= 2 , 0
                         5481.84         1539.59
Permanent Ineff=
       F       F
Bank Sta=4977.1,4992.4
XS Rating Curve= 0 ,0
Exp/Cntr=0.3,0.1

Type RM Length L Ch R = 1 ,8934    ,575,575,575
BEGIN DESCRIPTION:
Hasenwinkel Creek 12.0
END DESCRIPTION:
XS GIS Cut Line= 3
      1983515.29     13916506.26       1983227.9     13916418.21
      1982025.01       13916025.
#Sta/Elev= 30
    4697 1558.41  4752.1 1558.83  4758.4 1557.08    4767 1550.85  4777.2 1552.04
    4840 1548.93  4858.8  1547.7  4871.3  1545.2  4902.7 1544.79    4931 1540.96
  4962.3 1539.43  4968.6 1538.71  4990.6 1529.43  4999.9 1527.17  5001.9 1523.59
  5002.4 1523.09  5017.2 1523.59  5019.51524.756  5035.61531.236    5041 1535.04
  5047.3 1536.04  5179.9 1537.67  5268.3 1536.45  5361.5 1537.83  5688.1 1538.49
  5953.7 1534.84  6083.31537.739    6193 1543.29  6239.91551.297  6263.1 1552.42
#Mann= 7 ,-1 , 0
    4697     .07       0  5001.9     .05       0  5017.2     .05       0
  5019.5     .07       0  5035.6    .035       0  6083.3    .035       0
  6239.9    .063       0
Bank Sta=5001.9,5017.2
XS Rating Curve= 0 ,0
Exp/Cntr=0.3,0.1

Type RM Length L Ch R = 1 ,8359    ,476,476,476
BEGIN DESCRIPTION:
Hasenwinkel Creek 11.0
END DESCRIPTION:
XS GIS Cut Line= 5
      1983407.02     13915934.88        1983125.       13915875.
      1982516.39     13915909.01      1982321.87     13915922.71
      1982279.63     13915929.76
#Sta/Elev= 30
  4712.1 1541.79  4811.7 1538.69  4900.8 1533.21  4922.1 1532.79  4949.7 1533.73
  4958.9 1531.93    4965 1528.46  4983.4 1524.33  4986.5 1522.91  4989.6 1519.98
  4990.51517.814  4991.1 1516.37  4991.6 1515.87  5006.4 1516.37  5007.8 1524.38
  5010.8 1527.48  5016.8 1531.19  5027.8 1532.45  5060.81533.549  5088.9    1533
  5194.1 1534.74  5555.61534.968  5581.7 1534.94  5605.8 1536.07  5623.8 1534.46
  5674.9 1532.12  5713.7 1531.43  5797.9 1535.42  5822.4 1537.38  5847.8 1537.14
#Mann= 6 ,-1 , 0
  4712.1    .035       0  4990.5     .07       0  4991.1     .05       0
  5006.4     .05       0  5060.8    .035       0  5555.6     .07       0
#XS Ineff= 2 , 0
                         5607.62         1536.13
Permanent Ineff=
       F       F
Bank Sta=4991.1,5006.4
XS Rating Curve= 0 ,0
Exp/Cntr=0.3,0.1

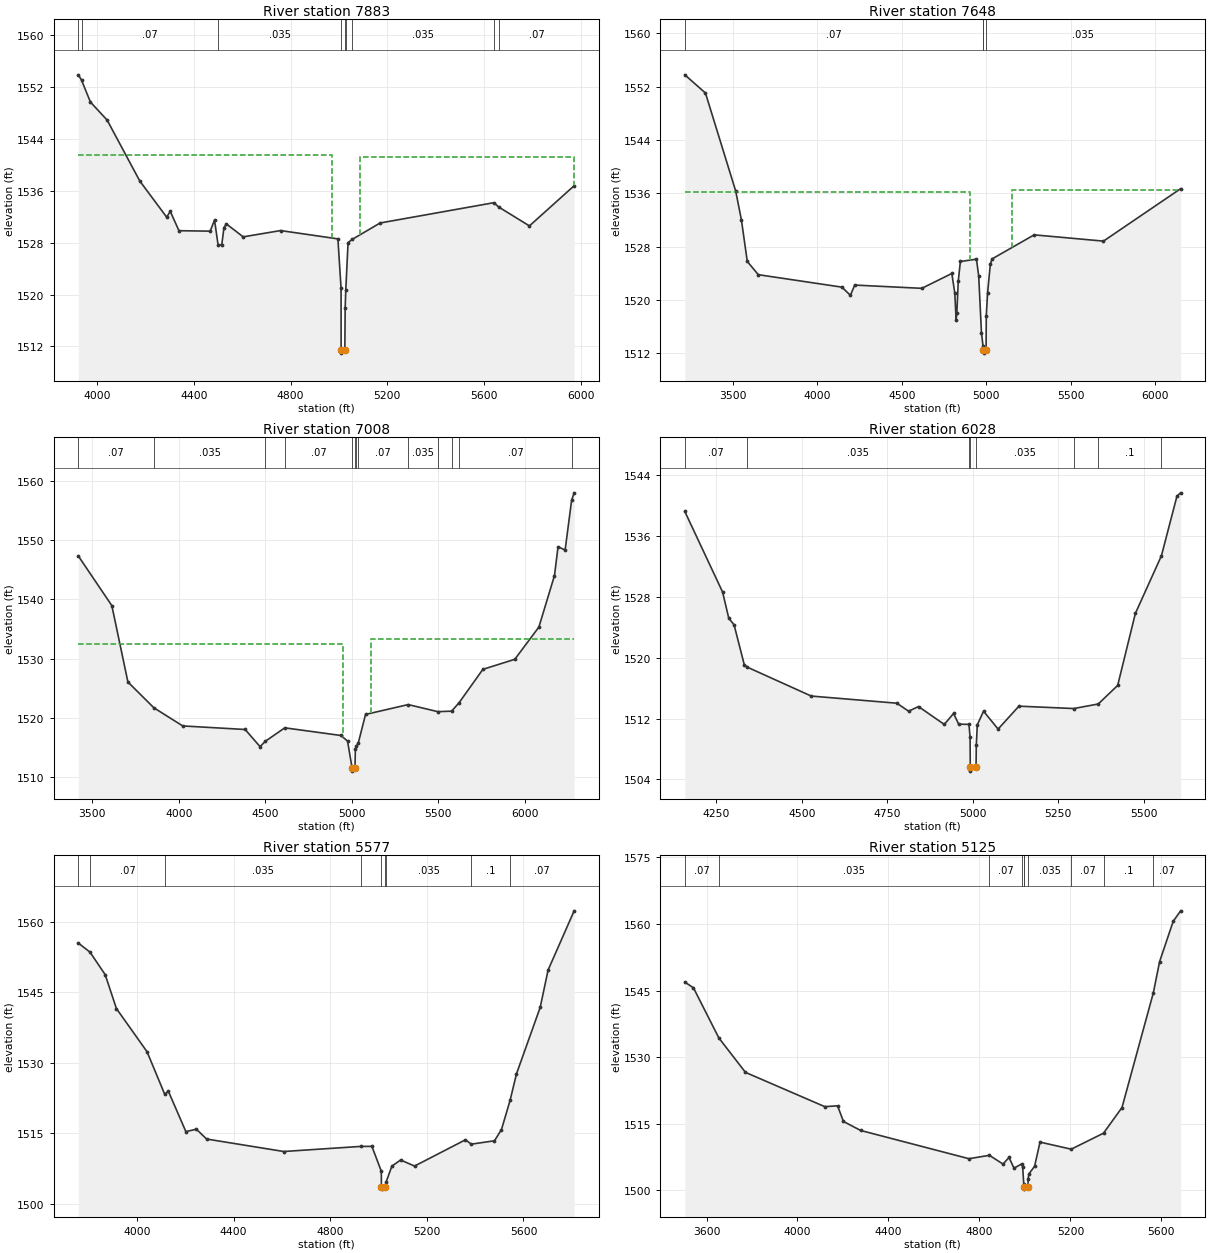
Type RM Length L Ch R = 1 ,7883    ,235,235,235
BEGIN DESCRIPTION:
Hasenwinkel Creek 10.0
END DESCRIPTION:
XS GIS Cut Line= 5
      1984202.59     13915435.82      1983168.18     13915430.04
      1983069.34     13915433.05      1982575.48     13915787.92
      1982295.65     13915916.96
#Sta/Elev= 30
  3922.8  1553.9  3935.9 1553.09  3972.8  1549.7  4041.8 1546.92  4176.8 1537.52
  4287.8 1531.95  4302.9 1532.83  4338.7 1529.85  4467.8 1529.78  4485.8 1531.49
  4500.8 1527.59  4515.8  1527.7  4524.8 1530.34    4535 1530.89  4604.2  1528.9
  4758.8 1529.87  4995.8 1528.59  5008.9 1520.96  5009.1 1511.46  5009.6 1510.96
  5024.5 1511.46  5025.8 1517.89  5028.4 1520.75  5037.8 1528.02    50561528.535
  5170.3 1531.04  5640.51534.171  5660.7  1533.5  5787.5 1530.59  5972.4 1536.79
#Mann= 9 ,-1 , 0
  3922.8      .1       0  3935.9     .07       0  4500.8    .035       0
  5009.1     .05       0  5024.5     .05       0  5028.4     .07       0
    5056    .035       0  5640.5    .035       0  5660.7     .07       0
#XS Ineff= 2 , 0
         4971.41  1541.5 5086.32         1541.23
Permanent Ineff=
       F       F
Bank Sta=5009.1,5024.5
XS Rating Curve= 0 ,0
Exp/Cntr=0.3,0.1

Type RM Length L Ch R = 1 ,7648    ,640,640,640
BEGIN DESCRIPTION:
Hasenwinkel Creek 8.0
END DESCRIPTION:
XS GIS Cut Line= 4
      1984406.42     13913968.66      1983243.51     13915143.95
       1983068.9     13915221.15      1982248.86     13915937.71
#Sta/Elev= 30
  3216.6 1553.79  3338.8 1551.06  3517.7 1536.34  3551.5 1532.02  3586.2 1525.77
  3651.5 1523.78  4145.8 1521.91  4196.7 1520.68  4221.7 1522.22  4618.8 1521.73
  4796.5 1523.96    4814 1521.02  4821.8 1517.02    4826 1517.98  4834.5  1522.8
  4847.1 1525.76  4942.2 1526.11  4955.5 1523.56  4971.8 1515.05  4981.21513.038
  4983.7  1512.5  4984.2    1512  4999.1  1512.5  5000.3 1517.63  5007.9 1521.02
  5024.2 1525.34  5034.1 1526.14  5283.4 1529.76  5693.6 1528.82  6150.1 1536.69
#Mann= 4 ,-1 , 0
  3216.6     .07       0  4981.2    .035       0  4983.7    .035       0
  4999.1    .035       0
#XS Ineff= 2 , 0
         4905.59 1536.15 5150.35         1536.45
Permanent Ineff=
       F       F
#Block Obstruct= 2 , 0
         4860.14 1523.37
Bank Sta=4983.7,4999.1
XS Rating Curve= 0 ,0
Exp/Cntr=0.3,0.1

Type RM Length L Ch R = 1 ,7008    ,980,980,980
BEGIN DESCRIPTION:
Hasenwinkel Creek 7.0
END DESCRIPTION:
XS GIS Cut Line= 4
      1984390.29     13913526.47      1983277.47     13914561.54
      1983126.21     13914649.26      1982269.41     13915446.24
#Sta/Elev= 30
    3420 1547.32  3613.5 1538.96  3706.4 1526.08  3856.4 1521.73  4023.2 1518.67
  4383.8 1518.07  4469.8 1515.18  4501.11516.094  4612.7 1518.35  4936.9 1517.06
  4975.5 1516.12  5001.8 1511.55  5002.3 1511.05  5018.5 1511.55  5020.6 1514.78
  5026.61515.259  5037.11515.748  5079.5 1520.61    5326 1522.27    54971521.076
  5576.61521.159  5619.71522.575  5757.4 1528.21  5941.7  1529.9    6081 1535.34
  6171.2 1544.03  6191.7 1548.88  6232.6 1548.32  6270.11556.716  6284.8 1557.97
#Mann= 13 ,-1 , 0
    3420     .07       0  3856.4    .035       0  4501.1     .07       0
  4612.7     .07       0  5001.8    .035       0  5018.5     .07       0
  5026.6    .035       0  5037.1     .07       0    5326    .035       0
    5497     .07       0  5576.6    .035       0  5619.7     .07       0
  6270.1    .035       0
#XS Ineff= 2 , 0
         4951.05 1532.46 5108.39         1533.25
Permanent Ineff=
       F       F
Bank Sta=5001.8,5018.5
XS Rating Curve= 0 ,0
Exp/Cntr=0.3,0.1

Type RM Length L Ch R = 1 ,6028    ,451,451,451
BEGIN DESCRIPTION:
Hasenwinkel Creek 6.0
END DESCRIPTION:
XS GIS Cut Line= 3
      1984262.56     13913588.31        1983425.       13913675.
      1982825.01       13913775.
#Sta/Elev= 30
    4158 1539.23  4268.5 1528.64  4286.6  1525.2  4302.2 1524.32  4331.9 1519.09
  4340.61518.762  4527.9 1514.96  4778.3 1514.02  4812.6 1512.97  4841.6 1513.58
    4917 1511.23  4944.1 1512.67  4959.2 1511.26  4989.21511.239  4992.4 1509.58
  4993.1 1505.59  4993.6 1505.09  5009.9 1505.59  5010.6 1508.48  5013.6 1511.18
  5031.9 1512.97  5074.4 1510.62  5135.3 1513.63  5295.8 1513.32  5367.21513.914
  5424.2 1516.36  5475.9 1525.82  5552.1  1533.4  5597.6 1541.25  5608.3 1541.68
#Mann= 8 ,-1 , 0
    4158     .07       0  4340.6    .035       0  4989.2    .035       0
  4993.1    .035       0  5009.9    .035       0  5295.8     .07       0
  5367.2      .1       0  5552.1     .07       0
Bank Sta=4993.1,5009.9
XS Rating Curve= 0 ,0
Exp/Cntr=0.3,0.1

Type RM Length L Ch R = 1 ,5577    ,452,452,452
BEGIN DESCRIPTION:
Hasenwinkel Creek 5.0
END DESCRIPTION:
XS GIS Cut Line= 3
      1984474.96     13912975.01        1983275.       13913275.
      1982675.03     13913824.98
#Sta/Elev= 30
  3757.3 1555.42  3805.41553.513  3868.5 1548.71  3914.9 1541.52  4041.7 1532.35
  4114.91523.305  4129.9 1523.97  4202.5 1515.38  4245.8  1515.9  4288.3 1513.81
  4607.6 1511.16  4927.31512.245  4972.5 1512.25  5011.5 1506.96  5011.9 1503.67
  5012.4 1503.17  5028.7 1503.67  5030.71504.597  5055.2 1508.05  5091.3 1509.36
  5149.1 1508.07  5359.9 1513.65  5383.71512.717  5479.9 1513.44  5508.7  1515.8
  5544.61522.042  5570.9 1527.64  5669.2 1541.78  5701.8 1549.69  5809.7 1562.27
#Mann= 9 ,-1 , 0
  3757.3      .1       0  3805.4     .07       0  4114.9    .035       0
  4927.3    .035       0  5011.9    .035       0  5028.7    .035       0
  5030.7    .035       0  5383.7      .1       0  5544.6     .07       0
Bank Sta=5011.9,5028.7
XS Rating Curve= 0 ,0
Exp/Cntr=0.3,0.1

Type RM Length L Ch R = 1 ,5125    ,462,462,462
BEGIN DESCRIPTION:
Hasenwinkel Creek 4.0
END DESCRIPTION:
XS GIS Cut Line= 3
      1984074.99     13912225.01        1982875.       13913125.
      1982474.98     13913675.03
#Sta/Elev= 30
  3504.5 1546.91  3542.5 1545.62  3654.31534.313  3771.2 1526.56    4120 1518.83
  4176.2 1519.02  4202.1 1515.49  4277.5 1513.47  4753.7  1507.1  4843.81507.861
  4903.7 1505.89    4930 1507.37  4952.1 1504.96  4986.11505.937    4990 1505.28
  4994.91501.414  4996.7 1500.74  4997.2 1500.24  5013.6 1500.74  5013.9 1502.55
  5017.6 1503.68  5042.4 1505.38  5066.4 1510.84  5203.51509.244  5345.51512.847
  5426.8 1518.63  5564.61544.487  5592.2 1551.52  5651.9  1560.6  5684.6 1562.97
#Mann= 10 ,-1 , 0
  3504.5     .07       0  3654.3    .035       0  4843.8     .07       0
  4986.1    .035       0  4994.9    .035       0  4996.7    .035       0
  5013.6    .035       0  5203.5     .07       0  5345.5      .1       0
  5564.6     .07       0
Bank Sta=4996.7,5013.6
XS Rating Curve= 0 ,0
Exp/Cntr=0.3,0.1

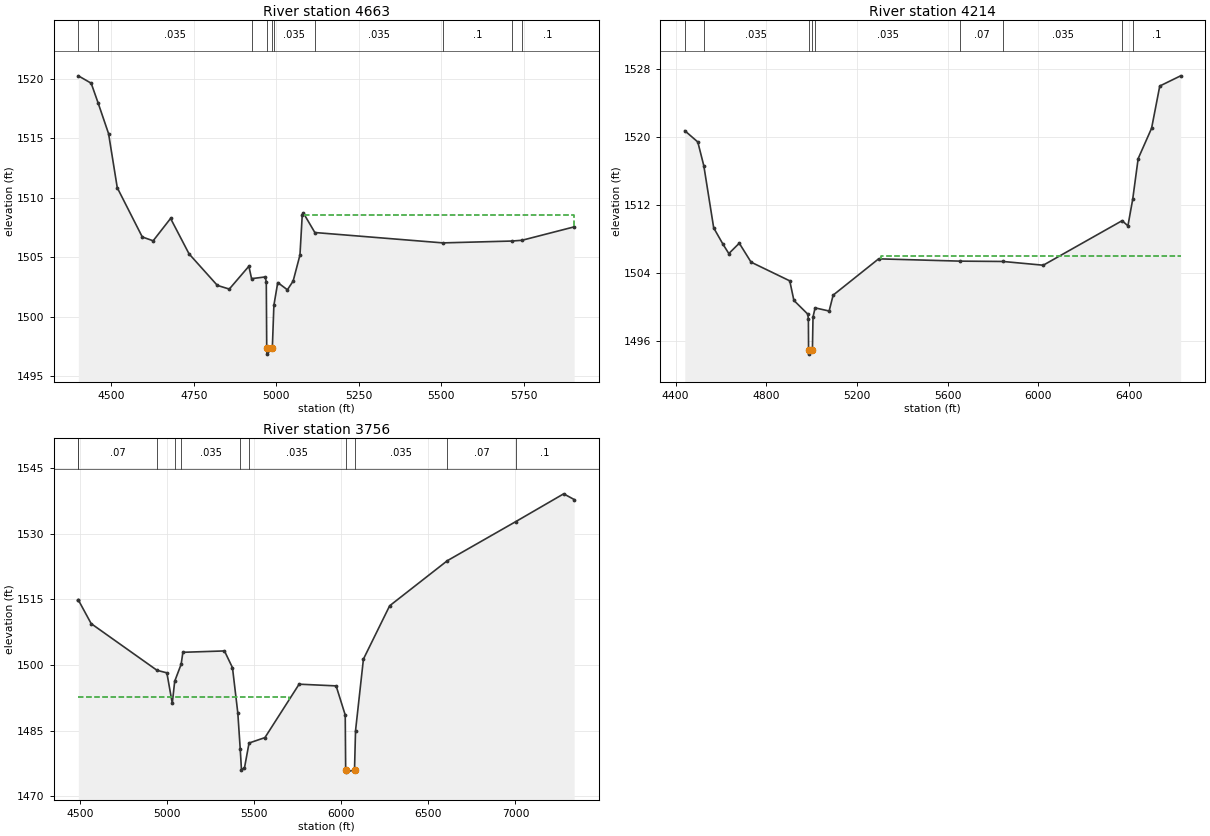
Type RM Length L Ch R = 1 ,4663    ,449,449,449
BEGIN DESCRIPTION:
Hasenwinkel Creek 3.0
END DESCRIPTION:
XS GIS Cut Line= 3
      1983225.02     13912474.99        1982675.       13912725.
      1981896.21     13913172.35
#Sta/Elev= 30
  4399.9 1520.24  4438.8 1519.62  4460.21517.932  4491.5 1515.38  4517.9 1510.83
  4593.7 1506.69  4626.6 1506.37  4679.4 1508.25  4735.4 1505.27  4821.1 1502.62
  4857.3 1502.31  4916.6 1504.23  4924.81503.186  4966.1 1503.33  4969.4  1502.9
  4970.7 1497.34  4971.2 1496.84  4987.7 1497.34  4992.4 1500.94  5004.1 1502.86
  5033.3 1502.25  5050.7 1502.98  5071.4 1505.17  5078.3 1508.52  5081.5 1508.72
  5116.51507.065  5504.21506.193  5714.11506.349  5744.41506.414  5902.2 1507.54
#Mann= 10 ,-1 , 0
  4399.9     .07       0  4460.2    .035       0  4924.8    .035       0
  4970.7    .035       0  4987.7    .035       0  4992.4    .035       0
  5116.5    .035       0  5504.2      .1       0  5714.1     .07       0
  5744.4      .1       0
#XS Ineff= 2 , 0
                         5083.86         1508.54
Permanent Ineff=
       F       F
Bank Sta=4970.7,4987.7
XS Rating Curve= 0 ,0
Exp/Cntr=0.3,0.1

Type RM Length L Ch R = 1 ,4214    ,458,458,458
BEGIN DESCRIPTION:
Hasenwinkel Creek 2.0
END DESCRIPTION:
XS GIS Cut Line= 3
      1983225.02       13912375.        1982675.       13912275.
      1981575.01     13913474.99
#Sta/Elev= 30
    4441 1520.78  4498.3 1519.46  4524.8 1516.67  4568.5 1509.35  4609.4 1507.43
  4635.2 1506.33  4681.3 1507.55  4733.3 1505.32  4903.9 1503.12  4922.2 1500.82
  4983.2 1499.21  4986.1 1498.66  4986.9    1495  4987.4  1494.5  5003.9    1495
  5006.5 1498.87  5015.71499.943  5077.6 1499.57  5095.3 1501.44  5295.9 1505.71
  5655.2 1505.44  5844.4  1505.4    6022 1504.96  6369.91510.199  6395.4 1509.59
  6416.41512.691  6440.6  1517.5  6499.8 1521.07  6535.9 1526.04  6627.9 1527.24
#Mann= 9 ,-1 , 0
    4441     .07       0  4524.8    .035       0  4986.9    .035       0
  5003.9    .035       0  5015.7    .035       0  5655.2     .07       0
  5844.4    .035       0  6369.9     .07       0  6416.4      .1       0
#XS Ineff= 2 , 0
                         5304.93         1506.06
Permanent Ineff=
       F       F
Bank Sta=4986.9,5003.9
XS Rating Curve= 0 ,0
Exp/Cntr=0.3,0.1

Type RM Length L Ch R = 1 ,3756    ,0,0,0
BEGIN DESCRIPTION:
Hasenwinkel Creek 1.0
END DESCRIPTION:
XS GIS Cut Line= 3
        1983025.       13911975.        1982525.       13911875.
      1980512.84      13910686.6
#Sta/Elev= 30
  4490.4 1514.86  4490.51514.862  4564.2 1509.46  4942.31498.803  4998.7 1498.23
  5029.8 1491.27  5043.71496.307  5080.81500.202  5090.7 1502.92  5329.4 1503.23
  5375.5  1499.4  5406.1 1489.05  5419.81480.911    5427 1476.15  5444.4 1476.54
  5470.61482.204  5561.7 1483.44    5758 1495.64  5970.5 1495.25  6022.8  1488.6
  6025.3 1476.06  6026.3 1475.56  6076.1 1476.06    6082 1485.03  6127.3 1501.37
  6277.9 1513.54  6609.3 1523.84  7002.9 1532.78    7277  1539.1  7337.2  1537.8
#Mann= 11 ,-1 , 0
  4490.4     .07       0  4490.5     .07       0  4942.3    .035       0
  5043.7     .07       0  5080.8    .035       0  5419.8    .035       0
  5470.6    .035       0  6025.3    .035       0  6076.1    .035       0
  6609.3     .07       0  7002.9      .1       0
#XS Ineff= 2 , 0
         5699.82 1492.67
Permanent Ineff=
       F       F
Bank Sta=6025.3,6076.1
XS Rating Curve= 0 ,0
Exp/Cntr=0.3,0.1

Chan Stop Cuts=-1
Use User Specified Reach Order=0
Composite Channel Slope=5