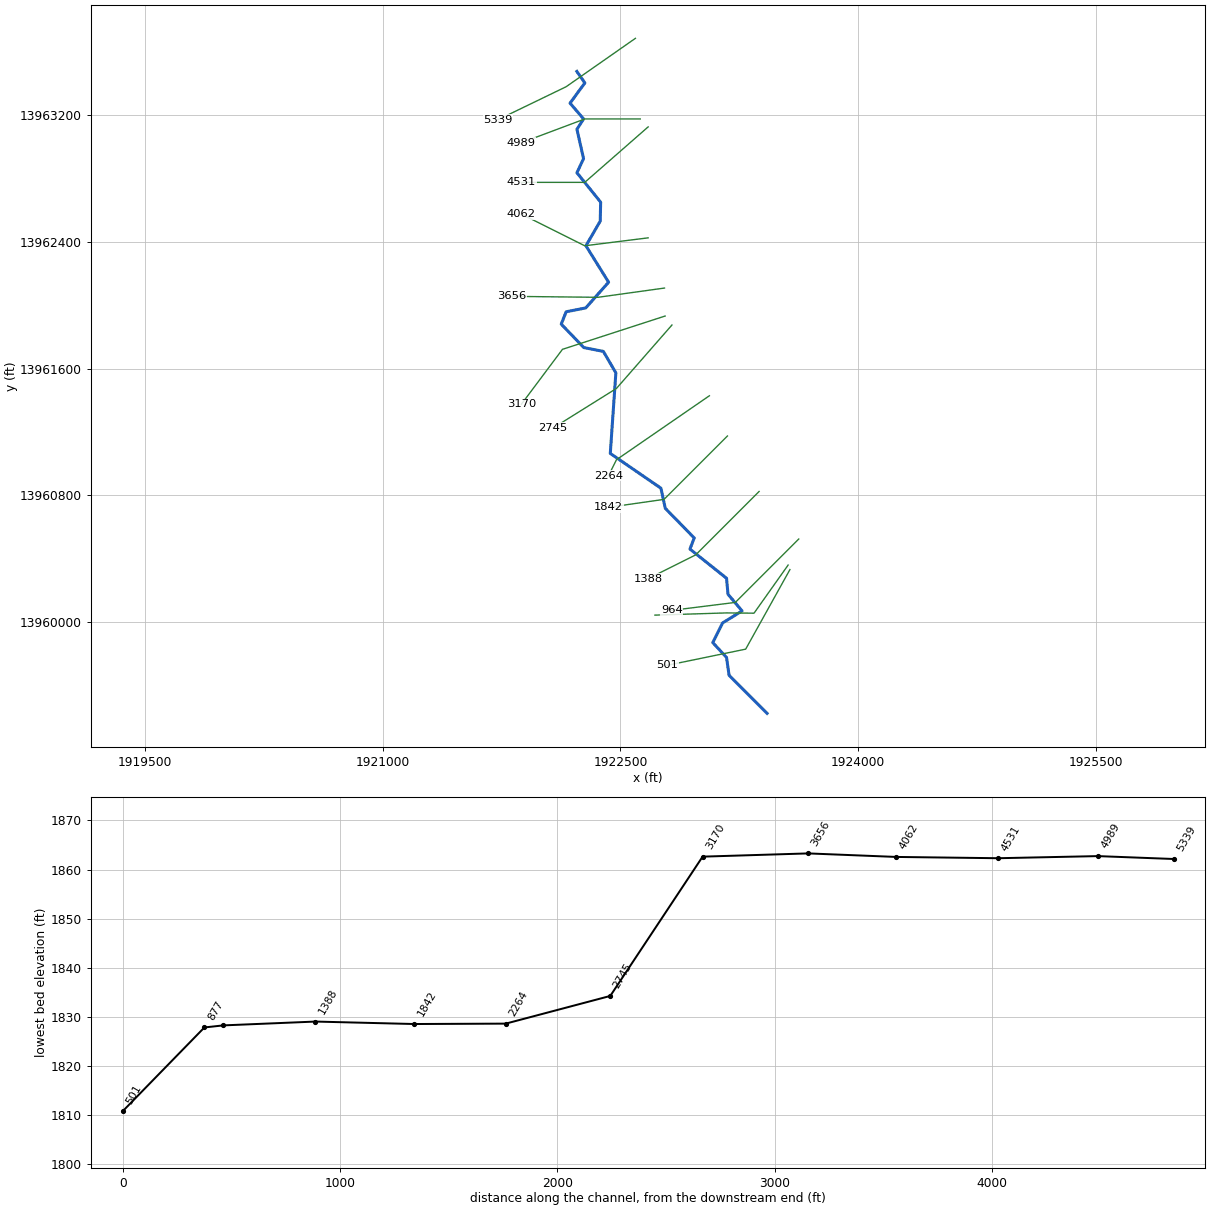
--- Indian Branch.prj (project) ---

Proj Title=Indian Branch Base Level Engineering
Current Plan=p01
Default Exp/Contr=0.3,0.1
English Units
Geom File=g01
Flow File=f01
Plan File=p01
BEGIN DESCRIPTION:
Indian Branch
END DESCRIPTION:

--- Indian Branch.p01 (plan) ---

Plan Title=Multiple Run
Short Identifier=Multiple
Geom File=g01
Flow File=f01
Subcritical Flow
K Sum by GR= 0
Std Step Tol= 0.01
Critical Tol= 0.01
Num of Std Step Trials= 20
Max Error Tol= 0.3
Flow Tol Ratio= 0.001
Split Flow NTrial= 30
Split Flow Tol= 0.02
Split Flow Ratio= 0.02
Log Output Level= 0
Friction Slope Method= 1
Unsteady Friction Slope Method= 2
Unsteady Bridges Friction Slope Method= 1
Parabolic Critical Depth
Global Vel Dist=  1 , 1 , 1
Global Log Level= 0
CheckData=True
Encroach Param= -1, 0, 0, 0
BEGIN DESCRIPTION:
Multiple Run
END DESCRIPTION:

--- Indian Branch.f01 (steady flow) ---

Flow Title=Multiple
Number of Profiles=7
Profile Names=10-year,25-year,50-year,1pct_min,100-year,1pct_plu,500-year
River Rch & RM= Indian Branch,Reach-1,5339
    1952    3443    4907    3374    6733   13434   12532
Boundary for River Rch & Prof#=Indian Branch,Reach-1,1
Up Type=0
Dn Type=3
Dn Slope=0.005
Boundary for River Rch & Prof#=Indian Branch,Reach-1,2
Up Type=0
Dn Type=3
Dn Slope=0.005
Boundary for River Rch & Prof#=Indian Branch,Reach-1,3
Up Type=0
Dn Type=3
Dn Slope=0.005
Boundary for River Rch & Prof#=Indian Branch,Reach-1,4
Up Type=0
Dn Type=3
Dn Slope=0.005
Boundary for River Rch & Prof#=Indian Branch,Reach-1,5
Up Type=0
Dn Type=3
Dn Slope=0.005
Boundary for River Rch & Prof#=Indian Branch,Reach-1,6
Up Type=0
Dn Type=3
Dn Slope=0.005
Boundary for River Rch & Prof#=Indian Branch,Reach-1,7
Up Type=0
Dn Type=3
Dn Slope=0.005

--- Indian Branch.g01 (geometry) ---

Geom Title=Existing Conditions

River Reach=Indian Branch,Reach-1
Reach XY= 30
      1922225.00     13963475.00      1922275.70     13963402.11
      1922182.11     13963275.00      1922267.66     13963175.10
      1922225.65     13963109.84      1922267.41     13962924.99
      1922225.65     13962835.64      1922375.32     13962650.11
      1922372.66     13962530.52      1922282.50     13962375.00
      1922425.47     13962145.16      1922281.17     13961982.86
      1922157.69     13961958.70      1922126.68     13961880.68
      1922268.83     13961732.86      1922392.13     13961708.70
      1922471.25     13961573.45      1922436.09     13961064.92
      1922755.53     13960845.54      1922782.86     13960718.83
      1922965.70     13960531.67      1922938.64     13960461.64
      1923169.48     13960277.44      1923178.64     13960176.50
      1923267.51     13960071.42      1923144.62     13959995.47
      1923082.78     13959871.60      1923169.45     13959777.43
      1923185.51     13959665.19      1923425.00     13959425.00

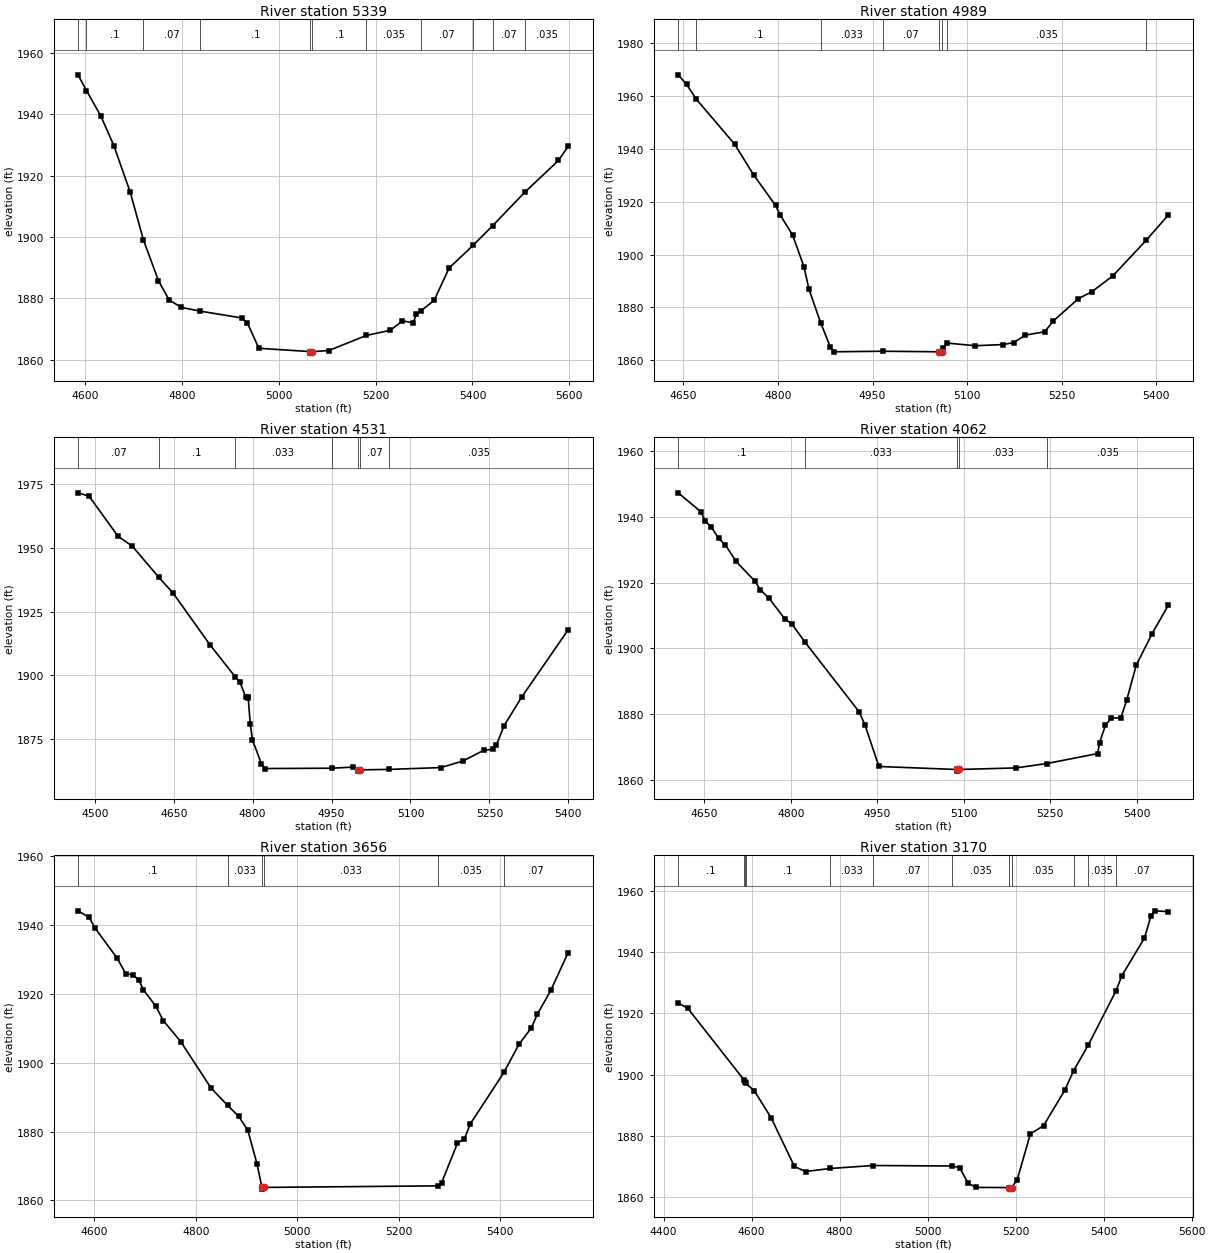
Type RM Length L Ch R = 1,5339,350,350,350
BEGIN DESCRIPTION:
Indian Branch 12.0
END DESCRIPTION:
XS GIS Cut Line= 3
      1922594.66     13963683.68      1922157.16     13963378.13
      1921726.65     13963169.82
#Sta/Elev= 30
  4585.6 1952.92  4603.0 1947.77  4632.4 1939.58  4659.5 1929.85  4693.1 1914.76
  4720.6 1899.09  4751.6 1885.80  4773.6 1879.49  4799.2 1877.05  4838.3 1875.83
  4923.6 1873.63  4935.3 1871.96  4959.0 1863.73  5064.8 1862.65  5065.2 1862.15
  5069.6 1862.65  5103.3 1862.99  5180.9 1867.91  5230.7 1869.62  5255.4 1872.68
  5277.7 1872.04  5284.3 1874.88  5293.8 1875.95  5321.0 1879.38  5351.9 1889.93
  5401.0 1897.26  5441.7 1903.71  5508.9 1914.75  5577.6 1924.98  5597.5 1929.59
#Mann=11,-1,0
  4585.6    0.07       0  4603.0     0.1       0  4720.6    0.07       0
  4838.3     0.1       0  5064.8    0.05       0  5069.6     0.1       0
  5180.9   0.035       0  5293.8    0.07       0  5401.0   0.035       0
  5441.7    0.07       0  5508.9   0.035       0
Bank Sta=5064.8,5069.6
Exp/Cntr=0.3,0.1

Type RM Length L Ch R = 1,4989,458,458,458
BEGIN DESCRIPTION:
Indian Branch 11.0
END DESCRIPTION:
XS GIS Cut Line= 3
      1922625.02     13963175.00      1922275.00     13963175.00
      1921875.02     13963025.01
#Sta/Elev= 30
  4641.6 1967.89  4655.1 1964.25  4670.3 1958.72  4731.2 1941.67  4761.2 1930.11
  4796.1 1918.53  4803.2 1915.01  4823.1 1907.37  4841.1 1895.38  4849.0 1886.96
  4867.5 1874.25  4883.1 1864.96  4889.1 1863.25  4966.1 1863.45  5055.9 1863.24
  5056.3 1862.74  5060.7 1863.24  5061.5 1864.62  5068.7 1866.53  5112.8 1865.54
  5157.5 1865.98  5173.7 1866.73  5192.4 1869.57  5222.7 1870.78  5236.7 1874.90
  5276.2 1883.29  5297.3 1885.89  5330.7 1891.86  5383.6 1905.30  5418.8 1914.88
#Mann=8,-1,0
  4641.6   0.035       0  4670.3     0.1       0  4867.5   0.033       0
  4966.1    0.07       0  5055.9    0.05       0  5060.7    0.07       0
  5068.7   0.035       0  5383.6     0.1       0
Bank Sta=5055.9,5060.7
Exp/Cntr=0.3,0.1

Type RM Length L Ch R = 1,4531,469,469,469
BEGIN DESCRIPTION:
Indian Branch 10.0
END DESCRIPTION:
XS GIS Cut Line= 3
      1922675.02     13963125.02      1922275.00     13962775.00
      1921875.04     13962775.00
#Sta/Elev= 30
  4468.1 1971.71  4489.1 1970.39  4544.2 1954.61  4571.5 1950.69  4621.7 1938.46
  4648.1 1932.49  4718.7 1912.02  4766.5 1899.47  4775.7 1897.37  4786.7 1891.52
  4791.0 1891.34  4791.6 1890.93  4795.6 1880.66  4799.6 1874.58  4816.5 1865.28
  4823.5 1863.33  4950.1 1863.46  4990.7 1863.89  4999.6 1862.81  4999.9 1862.31
  5004.5 1862.81  5059.9 1862.99  5158.1 1863.71  5200.1 1866.32  5239.1 1870.50
  5257.1 1870.89  5263.1 1872.44  5278.0 1880.21  5311.1 1891.34  5399.6 1917.81
#Mann=7,-1,0
  4468.1    0.07       0  4621.7     0.1       0  4766.5   0.033       0
  4950.1    0.07       0  4999.6    0.05       0  5004.5    0.07       0
  5059.9   0.035       0
Bank Sta=4999.6,5004.5
Exp/Cntr=0.3,0.1

Type RM Length L Ch R = 1,4062,406,406,406
BEGIN DESCRIPTION:
Indian Branch 9.0
END DESCRIPTION:
XS GIS Cut Line= 3
      1922675.00     13962425.00      1922275.00     13962375.00
      1921875.02     13962574.99
#Sta/Elev= 30
  4604.6 1947.39  4643.6 1941.69  4651.7 1938.80  4662.4 1936.90  4674.6 1933.53
  4686.6 1931.55  4704.8 1926.53  4738.1 1920.41  4747.2 1917.82  4762.3 1915.26
  4789.5 1909.00  4801.6 1907.49  4824.2 1901.99  4918.3 1880.72  4928.5 1876.77
  4952.9 1863.99  5087.7 1863.07  5088.1 1862.57  5092.7 1863.07  5190.9 1863.55
  5244.5 1864.89  5332.5 1867.92  5335.8 1871.22  5345.9 1876.51  5355.9 1878.77
  5372.7 1878.78  5382.8 1884.16  5399.5 1894.88  5426.4 1904.29  5454.9 1913.10
#Mann=5,-1,0
  4604.6     0.1       0  4824.2   0.033       0  5087.7   0.033       0
  5092.7   0.033       0  5244.5   0.035       0
Bank Sta=5087.7,5092.7
Exp/Cntr=0.3,0.1

Type RM Length L Ch R = 1,3656,486,486,486
BEGIN DESCRIPTION:
Indian Branch 8.0
END DESCRIPTION:
XS GIS Cut Line= 3
      1922778.17     13962108.27      1922357.92     13962049.85
      1921815.95     13962055.86
#Sta/Elev= 30
  4567.9 1944.18  4590.1 1942.25  4600.7 1939.31  4645.3 1930.36  4661.8 1925.95
  4675.6 1925.60  4687.7 1924.10  4696.8 1921.23  4721.0 1916.50  4736.1 1912.25
  4770.9 1906.06  4830.0 1892.69  4862.9 1887.61  4884.6 1884.46  4902.7 1880.40
  4920.9 1870.56  4930.5 1863.79  4930.9 1863.29  4935.5 1863.79  5277.7 1864.24
  5284.6 1865.05  5316.1 1876.68  5329.6 1877.88  5341.6 1882.31  5407.8 1897.24
  5437.5 1905.43  5461.6 1910.12  5473.6 1914.13  5500.6 1921.23  5534.2 1932.01
#Mann=6,-1,0
  4567.9     0.1       0  4862.9   0.033       0  4930.5   0.033       0
  4935.5   0.033       0  5277.7   0.035       0  5407.8    0.07       0
Bank Sta=4930.5,4935.5
Exp/Cntr=0.3,0.1

Type RM Length L Ch R = 1,3170,425,425,425
BEGIN DESCRIPTION:
Indian Branch 7.0
END DESCRIPTION:
XS GIS Cut Line= 3
      1922781.89     13961931.75      1922134.34     13961721.68
      1921875.01     13961375.02
#Sta/Elev= 30
  4433.0 1923.37  4454.4 1921.73  4582.9 1898.23  4584.8 1897.74  4587.2 1897.13
  4606.2 1894.69  4644.3 1885.92  4697.2 1870.03  4722.5 1868.37  4778.7 1869.37
  4876.2 1870.34  5056.3 1870.18  5072.6 1869.64  5092.0 1864.51  5110.4 1863.20
  5186.0 1863.13  5186.4 1862.63  5191.1 1863.13  5203.6 1865.75  5233.5 1880.70
  5263.3 1883.31  5312.1 1895.04  5331.8 1901.31  5364.6 1909.54  5427.9 1927.31
  5441.4 1932.31  5492.8 1944.61  5507.8 1951.93  5516.4 1953.47  5546.7 1953.22
#Mann=12,-1,0
  4433.0     0.1       0  4582.9   0.035       0  4584.8    0.07       0
  4587.2     0.1       0  4778.7   0.033       0  4876.2    0.07       0
  5056.3   0.035       0  5186.0    0.05       0  5191.1   0.035       0
  5331.8     0.1       0  5364.6   0.035       0  5427.9    0.07       0
Bank Sta=5186,5191.1
Exp/Cntr=0.3,0.1

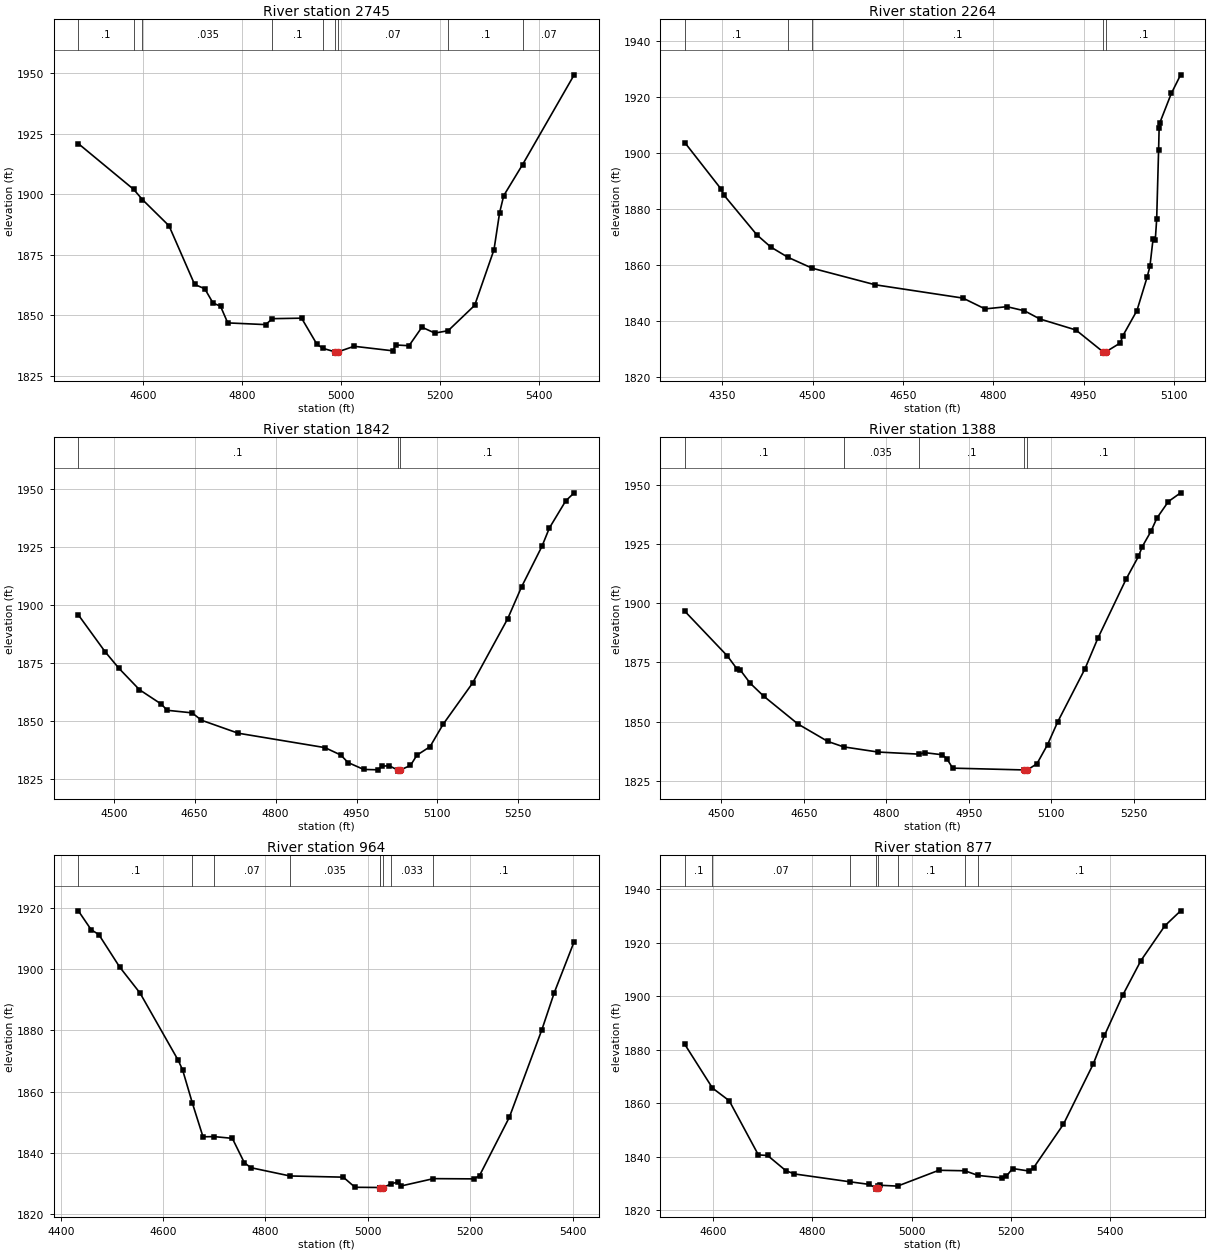
Type RM Length L Ch R = 1,2745,481,481,481
BEGIN DESCRIPTION:
Indian Branch 6.0
END DESCRIPTION:
XS GIS Cut Line= 3
      1922825.01     13961875.01      1922475.00     13961475.00
      1922075.01     13961225.01
#Sta/Elev= 30
  4468.6 1920.87  4580.6 1901.94  4598.3 1897.72  4652.1 1886.89  4703.9 1862.65
  4724.4 1860.87  4741.1 1854.96  4756.3 1853.64  4770.9 1846.75  4847.4 1846.04
  4861.4 1848.50  4920.3 1848.70  4951.6 1837.82  4964.2 1836.19  4988.4 1834.75
  4988.8 1834.25  4993.5 1834.75  5026.6 1837.08  5104.4 1835.22  5111.5 1837.61
  5137.7 1837.32  5163.8 1844.97  5189.9 1842.54  5216.8 1843.52  5270.5 1854.01
  5309.6 1877.00  5321.0 1892.36  5329.3 1899.37  5367.5 1912.22  5471.8 1949.31
#Mann=9,-1,0
  4468.6     0.1       0  4580.6    0.07       0  4598.3   0.035       0
  4861.4     0.1       0  4964.2    0.07       0  4988.4    0.05       0
  4993.5    0.07       0  5216.8     0.1       0  5367.5    0.07       0
Bank Sta=4988.4,4993.5
Exp/Cntr=0.3,0.1

Type RM Length L Ch R = 1,2264,422,422,422
BEGIN DESCRIPTION:
Indian Branch 5.0
END DESCRIPTION:
XS GIS Cut Line= 3
      1923061.22     13961428.76      1922475.00     13961025.00
      1922425.01     13960925.02
#Sta/Elev= 30
  4287.6 1903.78  4347.3 1887.35  4352.7 1885.00  4407.4 1870.82  4430.3 1866.51
  4458.6 1862.86  4499.2 1858.93  4604.1 1853.00  4749.6 1848.26  4786.3 1844.40
  4822.7 1845.19  4851.8 1843.72  4877.3 1840.81  4937.3 1836.87  4982.1 1829.11
  4982.5 1828.61  4987.3 1829.11  5011.0 1832.24  5015.2 1834.80  5038.6 1843.78
  5055.7 1855.84  5060.2 1859.61  5065.5 1869.53  5069.1 1868.99  5071.4 1876.34
  5074.6 1900.97  5075.5 1908.98  5076.5 1910.76  5095.7 1921.31  5111.2 1927.97
#Mann=5,-1,0
  4287.6     0.1       0  4458.6    0.07       0  4499.2     0.1       0
  4982.1    0.05       0  4987.3     0.1       0
Bank Sta=4982.1,4987.3
Exp/Cntr=0.3,0.1

Type RM Length L Ch R = 1,1842,454,454,454
BEGIN DESCRIPTION:
Indian Branch 4.0
END DESCRIPTION:
XS GIS Cut Line= 3
      1923175.01     13961175.01      1922775.00     13960775.00
      1922425.05     13960725.01
#Sta/Elev= 30
  4434.3 1895.80  4483.9 1879.93  4509.4 1872.83  4547.6 1863.58  4588.1 1857.38
  4599.0 1854.72  4645.2 1853.61  4662.4 1850.46  4730.5 1844.86  4891.5 1838.65
  4920.9 1835.46  4934.2 1832.24  4963.4 1829.25  4989.1 1829.11  4997.3 1830.65
  5010.6 1830.86  5026.1 1829.03  5026.5 1828.53  5031.3 1829.03  5050.0 1830.97
  5062.1 1835.42  5086.3 1839.05  5110.6 1848.71  5165.1 1866.42  5230.3 1894.14
  5256.0 1907.85  5293.9 1925.35  5307.5 1933.16  5337.9 1944.87  5353.5 1948.33
#Mann=3,-1,0
  4434.3     0.1       0  5026.1    0.05       0  5031.3     0.1       0
Bank Sta=5026.1,5031.3
Exp/Cntr=0.3,0.1

Type RM Length L Ch R = 1,1388,424,424,424
BEGIN DESCRIPTION:
Indian Branch 3.0
END DESCRIPTION:
XS GIS Cut Line= 3
      1923375.00     13960825.00      1922975.00     13960425.00
      1922675.00     13960275.00
#Sta/Elev= 30
  4433.7 1896.69  4511.2 1877.73  4529.1 1872.09  4534.5 1871.81  4552.6 1866.21
  4576.9 1860.79  4639.4 1848.96  4693.6 1841.60  4722.2 1839.30  4784.8 1837.11
  4859.6 1836.21  4869.7 1836.85  4901.5 1835.96  4910.0 1834.25  4920.6 1830.29
  5050.9 1829.53  5051.3 1829.03  5056.2 1829.53  5073.7 1832.16  5093.0 1840.25
  5111.4 1849.87  5160.9 1872.29  5184.4 1885.26  5236.1 1910.45  5258.2 1919.90
  5265.1 1924.03  5280.8 1930.46  5291.7 1936.11  5312.6 1943.11  5334.8 1946.79
#Mann=5,-1,0
  4433.7     0.1       0  4722.2   0.035       0  4859.6     0.1       0
  5050.9    0.05       0  5056.2     0.1       0
Bank Sta=5050.9,5056.2
Exp/Cntr=0.3,0.1

Type RM Length L Ch R = 1,964,87,87,87
BEGIN DESCRIPTION:
Indian Branch 2.0
END DESCRIPTION:
XS GIS Cut Line= 3
      1923625.01     13960525.01      1923225.00     13960125.00
      1922825.01     13960075.00
#Sta/Elev= 30
  4434.4 1918.95  4459.5 1912.79  4474.4 1911.22  4515.1 1900.65  4555.0 1892.14
  4629.7 1870.19  4638.2 1867.07  4657.3 1856.24  4678.0 1845.30  4699.6 1845.37
  4735.3 1844.80  4758.7 1836.88  4771.4 1835.24  4847.9 1832.54  4952.1 1832.15
  4975.0 1828.85  5024.3 1828.78  5024.4 1828.75  5024.8 1828.25  5029.7 1828.75
  5045.1 1829.94  5059.0 1830.59  5065.1 1829.28  5128.3 1831.67  5207.5 1831.59
  5218.3 1832.66  5276.7 1851.72  5340.2 1880.24  5364.4 1892.31  5403.2 1908.90
#Mann=9,-1,0
  4434.4     0.1       0  4657.3   0.035       0  4699.6    0.07       0
  4847.9   0.035       0  5024.3     0.1       0  5024.4   0.035       0
  5029.7     0.1       0  5045.1   0.033       0  5128.3     0.1       0
Bank Sta=5024.4,5029.7
Exp/Cntr=0.3,0.1

Type RM Length L Ch R = 1,877,376,376,376
BEGIN DESCRIPTION:
Indian Branch 0.1
END DESCRIPTION:
XS GIS Cut Line= 4
      1923558.09     13960360.82      1923342.83     13960057.02
      1923169.22     13960058.76      1922717.79     13960044.87
#Sta/Elev= 30
  4543.7 1881.99  4599.4 1865.64  4633.1 1860.90  4691.7 1840.64  4710.3 1840.42
  4747.0 1834.74  4764.3 1833.51  4875.3 1830.59  4914.8 1829.60  4927.7 1828.33
  4928.1 1827.83  4933.0 1828.33  4933.3 1829.14  4936.3 1829.28  4971.7 1828.96
  5054.8 1834.88  5107.2 1834.70  5133.7 1832.95  5182.4 1832.03  5190.1 1832.57
  5203.4 1835.54  5236.4 1834.59  5245.4 1835.81  5305.4 1852.07  5365.5 1874.64
  5388.1 1885.34  5425.5 1900.64  5461.5 1913.37  5509.5 1926.34  5541.3 1931.96
#Mann=8,-1,0
  4543.7     0.1       0  4599.4    0.07       0  4875.3   0.035       0
  4927.7    0.05       0  4933.0   0.035       0  4971.7     0.1       0
  5107.2   0.033       0  5133.7     0.1       0
Bank Sta=4927.7,4933
Exp/Cntr=0.3,0.1

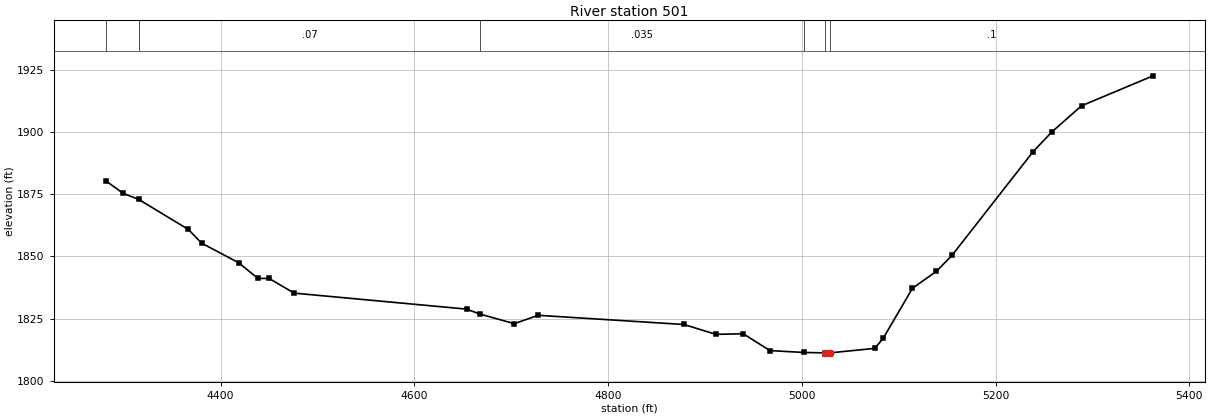
Type RM Length L Ch R = 1,501,0,0,0
BEGIN DESCRIPTION:
Indian Branch 0.0
END DESCRIPTION:
XS GIS Cut Line= 3
      1923569.47     13960332.27      1923290.15     13959830.20
      1922794.30     13959728.07
#Sta/Elev= 30
  4281.7 1880.32  4299.6 1875.31  4315.5 1872.90  4366.8 1860.83  4380.5 1855.32
  4418.7 1847.47  4438.5 1841.18  4450.2 1841.14  4476.0 1835.26  4653.9 1828.84
  4668.1 1826.82  4703.2 1822.99  4727.9 1826.35  4878.3 1822.66  4911.2 1818.71
  4939.6 1818.92  4967.1 1812.18  5002.1 1811.43  5023.6 1811.26  5024.0 1810.76
  5028.9 1811.26  5075.2 1813.07  5083.9 1817.06  5114.2 1837.22  5138.7 1843.95
  5155.0 1850.43  5238.8 1892.12  5258.1 1900.01  5288.7 1910.49  5362.5 1922.52
#Mann=6,-1,0
  4281.7     0.1       0  4315.5    0.07       0  4668.1   0.035       0
  5002.1     0.1       0  5023.6   0.035       0  5028.9     0.1       0
Bank Sta=5023.6,5028.9
Exp/Cntr=0.3,0.1

Chan Stop Cuts=-1