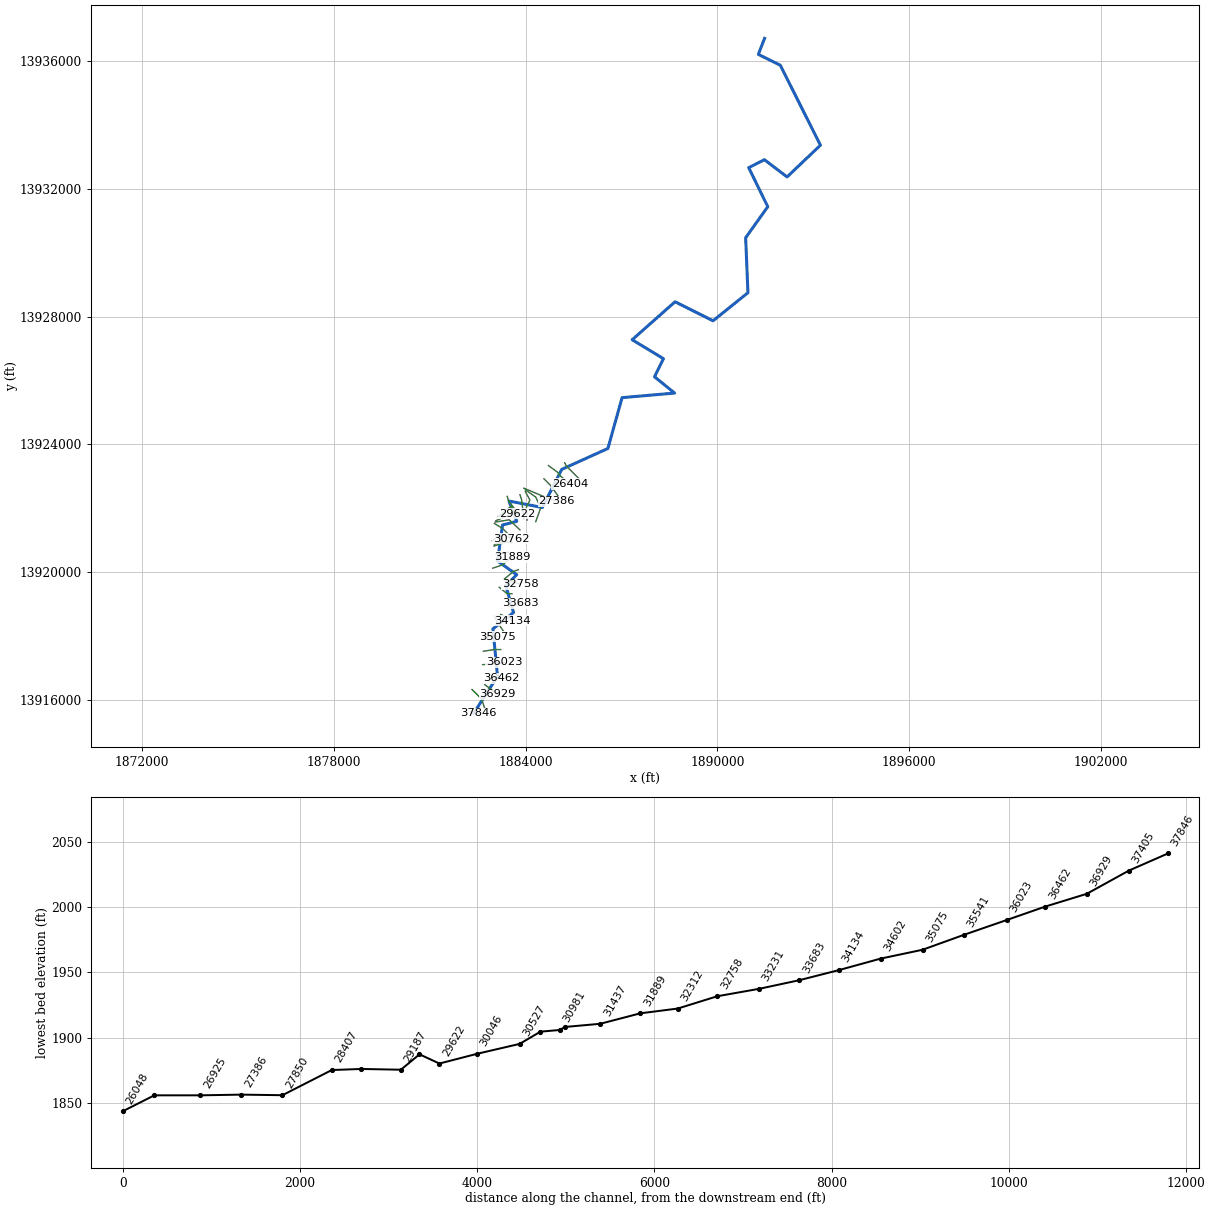
--- Indian Creek 03.prj (project) ---

Proj Title=Indian Creek 03 Base Level Engineering
Current Plan=p01
Default Exp/Contr=0.3,0.1
English Units
Geom File=g01
Flow File=f01
Plan File=p01
Y Axis Title=Elevation
X Axis Title(PF)=Main Channel Distance
X Axis Title(XS)=Station
BEGIN DESCRIPTION:
Indian Creek 03
END DESCRIPTION:
DSS Export Rating Curves= 0
DSS Export Rating Curve Sorted= 0
DSS Export Volume Flow Curves= 0
DXF OffsetX= 0
DXF OffsetY= 0
DXF ScaleX= 1
DXF ScaleY= 10

--- Indian Creek 03.p01 (plan) ---

Plan Title=Multiple Run
Short Identifier=Multiple
Geom File=g01
Flow File=f01
Subcritical Flow
K Sum by GR= 0
Std Step Tol= 0.01
Critical Tol= 0.01
Num of Std Step Trials= 20
Max Error Tol= 0.3
Flow Tol Ratio= 0.001
Split Flow NTrial= 30
Split Flow Tol= 0.02
Split Flow Ratio= 0.02
Log Output Level= 0
Friction Slope Method= 1
Unsteady Friction Slope Method= 2
Unsteady Bridges Friction Slope Method= 1
Parabolic Critical Depth
Global Vel Dist=  1 , 1 , 1
Global Log Level= 0
CheckData=True
Encroach Param= -1, 0, 0, 0
BEGIN DESCRIPTION:
Multiple Run
END DESCRIPTION:

--- Indian Creek 03.f01 (steady flow) ---

Flow Title=Multiple
Number of Profiles=7
Profile Names=10-year,25-year,50-year,1pct_min,100-year,1pct_plu,500-year
River Rch & RM= Indian Creek 03,Reach-1,37846
    1288    2228    3133    2130    4251    8481    7728
River Rch & RM= Indian Creek 03,Reach-1,29187
    1849    3263    4653    3203    6391   12751   11918
River Rch & RM= Indian Creek 03,Reach-1,27386
    2106    3731    5333    3678    7338   14641   13733
River Rch & RM= Indian Creek 03,Reach-1,24434
    2246    3991    5717    3949    7878   15719   14798
River Rch & RM= Indian Creek 03,Reach-1,23237
    3050    5504    7966    5553   11079   22106   21204
River Rch & RM= Indian Creek 03,Reach-1,21854
    3090    5560    8029    5583   11139   22225   21212
River Rch & RM= Indian Creek 03,Reach-1,17229
    3365    6072    8783    6115   12202   24346   23301
River Rch & RM= Indian Creek 03,Reach-1,14140
    4812    8820   12894    9064   18085   36085   35207
River Rch & RM= Indian Creek 03,Reach-1,11922
    5127    9404   13754    9670   19293   38495   37565
River Rch & RM= Indian Creek 03,Reach-1,7620
    5269    9645   14086    9886   19725   39356   38271
Boundary for River Rch & Prof#=Indian Creek 03,Reach-1,1
Up Type=0
Dn Type=3
Dn Slope=0.005
Boundary for River Rch & Prof#=Indian Creek 03,Reach-1,2
Up Type=0
Dn Type=3
Dn Slope=0.005
Boundary for River Rch & Prof#=Indian Creek 03,Reach-1,3
Up Type=0
Dn Type=3
Dn Slope=0.005
Boundary for River Rch & Prof#=Indian Creek 03,Reach-1,4
Up Type=0
Dn Type=3
Dn Slope=0.005
Boundary for River Rch & Prof#=Indian Creek 03,Reach-1,5
Up Type=0
Dn Type=3
Dn Slope=0.005
Boundary for River Rch & Prof#=Indian Creek 03,Reach-1,6
Up Type=0
Dn Type=3
Dn Slope=0.005
Boundary for River Rch & Prof#=Indian Creek 03,Reach-1,7
Up Type=0
Dn Type=3
Dn Slope=0.005

--- Indian Creek 03.g01 (geometry) ---

Geom Title=Existing Conditions
Program Version=4.10

River Reach=Indian Creek 03 ,Reach-1
Reach XY= 30
        1882375.       13915575.      1883123.92     13916735.55
      1882978.75     13918223.45       1883623.9     13918735.55
      1883382.32      13919575.1      1883723.44     13919918.91
      1883124.64      13920349.8      1883280.34     13921477.74
      1883724.78       13921591.      1883480.13     13922227.94
        1884525.       13922025.      1885130.63     13923219.35
        1886575.       13923875.      1887018.81     13925467.19
      1888661.88       13925611.      1888032.68     13926121.29
      1888311.48     13926688.38      1887334.12     13927281.74
      1888676.25     13928471.55      1889863.16     13927875.59
      1890955.22     13928754.91      1890883.08      13930478.3
      1891575.54     13931450.13      1890978.45     13932673.52
      1891469.16     13932922.95      1892178.33       13932383.
      1893221.69     13933376.74      1891967.14     13935881.17
      1891280.09      13936222.7        1891475.       13936725.

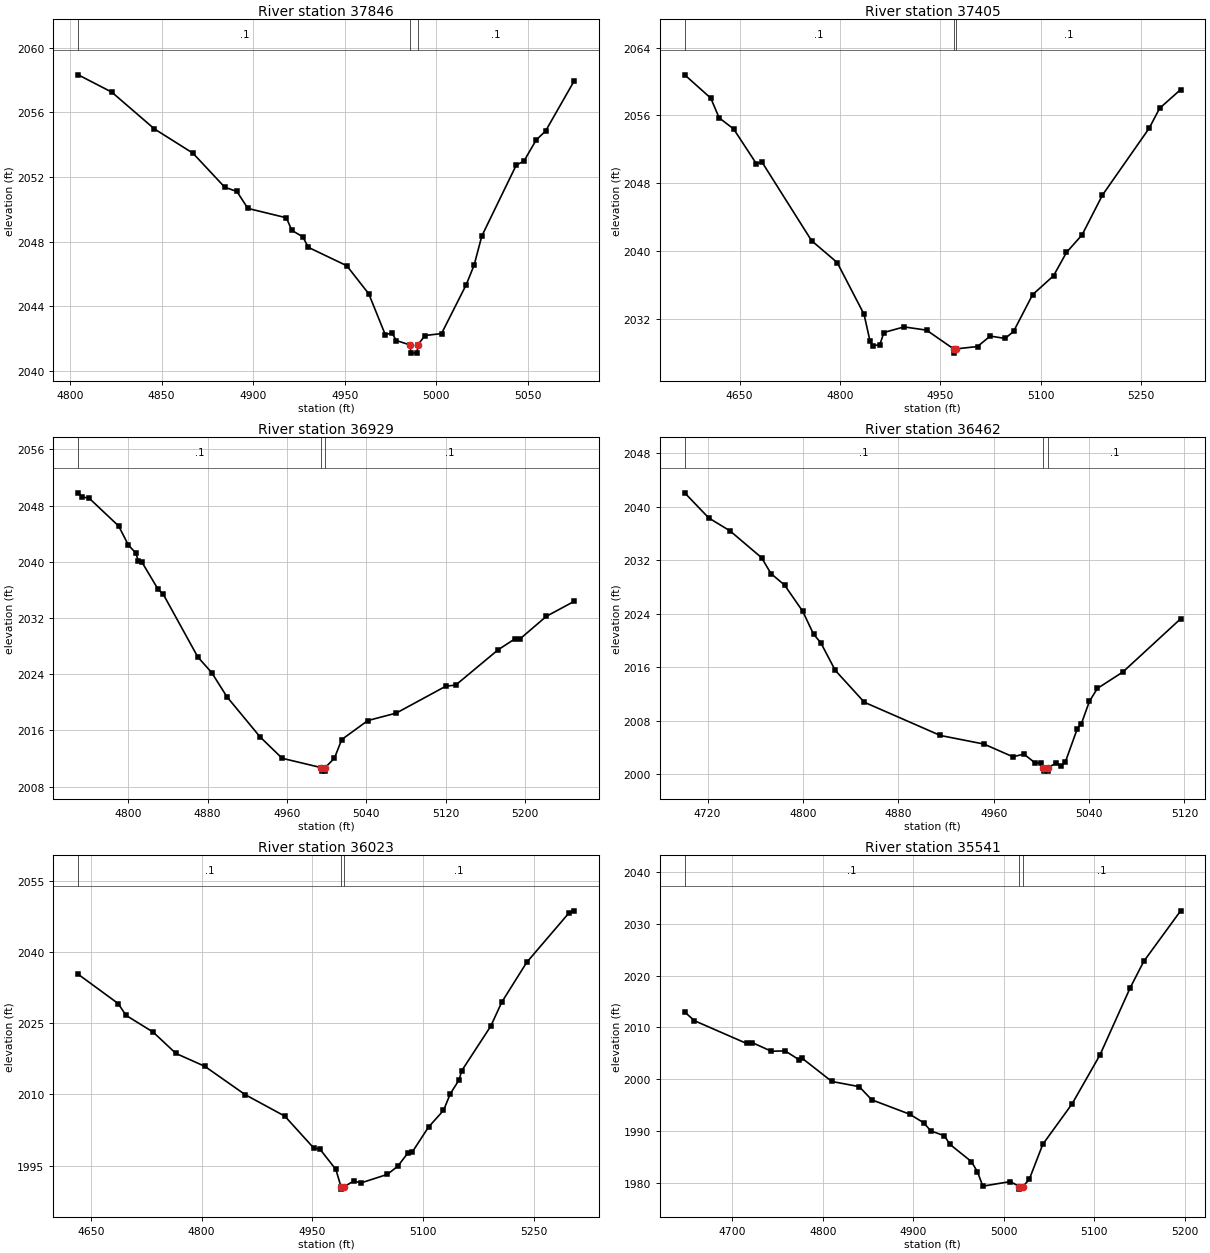
Type RM Length L Ch R = 1 ,37846   ,441,441,441
BEGIN DESCRIPTION:
Indian Creek 03 79.0
END DESCRIPTION:
XS GIS Cut Line= 3
        1882275.       13915625.        1882475.       13915625.
      1882524.99     13915575.01
#Sta/Elev= 30
  4804.5 2058.33  4822.8 2057.26  4846.1 2054.98  4867.1 2053.48  4884.5 2051.37
  4891.1 2051.11  4897.1 2050.06  4918.1 2049.48  4921.1  2048.7  4927.1  2048.3
  4930.1 2047.65  4951.1 2046.51  4963.1 2044.77  4972.1 2042.24  4975.8 2042.35
  4978.1 2041.88  4985.8  2041.6    4986  2041.1  4989.5  2041.1  4989.8  2041.6
  4993.8 2042.19  5002.8 2042.31  5016.3 2045.34  5020.6 2046.55  5024.8 2048.35
  5043.6 2052.74  5047.8 2052.99  5054.5  2054.3  5059.6 2054.85  5075.2 2057.95
#Mann= 3 ,-1 , 0
  4804.5      .1       0  4985.8     .05       0  4989.8      .1       0
Bank Sta=4985.8,4989.8
XS Rating Curve= 0 ,0
Exp/Cntr=0.3,0.1

Type RM Length L Ch R = 1 ,37405   ,476,476,476
BEGIN DESCRIPTION:
Indian Creek 03 78.0
END DESCRIPTION:
XS GIS Cut Line= 3
      1882325.01     13916324.99        1882625.       13916025.
      1882725.01     13915724.97
#Sta/Elev= 30
  4568.1 2060.79  4607.1 2058.04  4619.5 2055.72  4641.1 2054.42    4675 2050.33
  4683.5 2050.51  4757.6 2041.24  4795.8 2038.67  4835.9 2032.57  4844.7 2029.45
  4848.6 2028.87  4859.4 2028.97  4865.6 2030.42  4895.6 2031.08  4929.2  2030.7
  4969.6 2028.49  4969.9 2027.99  4973.6 2028.49  5005.4 2028.77  5024.3    2030
  5046.5 2029.72  5059.1 2030.54  5087.6 2034.88  5118.8  2037.1  5138.2 2039.86
  5161.5 2041.93  5191.9 2046.62  5261.5 2054.48  5277.3 2056.85  5308.6 2059.05
#Mann= 3 ,-1 , 0
  4568.1      .1       0  4969.6     .05       0  4973.6      .1       0
Bank Sta=4969.6,4973.6
XS Rating Curve= 0 ,0
Exp/Cntr=0.3,0.1

Type RM Length L Ch R = 1 ,36929   ,467,467,467
BEGIN DESCRIPTION:
Indian Creek 03 77.0
END DESCRIPTION:
XS GIS Cut Line= 3
      1882725.02     13916474.99        1882925.       13916325.
      1883125.02     13916174.99
#Sta/Elev= 30
  4749.6 2049.81  4753.8 2049.18  4760.3 2049.09  4790.4 2045.08  4800.2 2042.37
  4807.4 2041.27  4810.2 2040.16  4813.8 2039.95  4830.2 2036.06  4835.3 2035.38
  4870.2 2026.43  4884.1 2024.23  4899.6 2020.76  4932.9 2015.07  4955.2 2012.02
  4994.6 2010.69  4994.9 2010.19  4998.4 2010.19  4998.6 2010.69  5007.9 2012.03
  5015.3 2014.69  5041.6 2017.39  5070.2 2018.45  5120.2 2022.28  5130.2 2022.44
  5172.9 2027.46  5190.2 2029.05  5195.4 2029.06  5221.6 2032.23  5249.6 2034.36
#Mann= 3 ,-1 , 0
  4749.6      .1       0  4994.6     .05       0  4998.6      .1       0
Bank Sta=4994.6,4998.6
XS Rating Curve= 0 ,0
Exp/Cntr=0.3,0.1

Type RM Length L Ch R = 1 ,36462   ,439,439,439
BEGIN DESCRIPTION:
Indian Creek 03 76.0
END DESCRIPTION:
XS GIS Cut Line= 3
      1882824.99       13916675.        1883125.       13916725.
      1883225.04     13916674.98
#Sta/Elev= 30
  4700.8 2042.08    4721 2038.32  4738.9 2036.38  4765.3 2032.38  4773.2    2030
  4784.6 2028.28  4799.8 2024.37  4808.9 2020.94  4814.9 2019.68  4827.1 2015.53
  4851.5 2010.76  4915.3 2005.79  4951.8 2004.51  4976.2  2002.6  4985.3 2003.01
  4994.4 2001.74    5000 2001.65  5001.5 2000.96  5001.8 2000.46  5005.3 2000.46
  5005.5 2000.96  5012.2 2001.65  5016.1 2001.18  5020.2 2001.88  5030.2 2006.83
  5033.6 2007.57  5040.3  2010.9    5047 2012.83  5068.4 2015.29  5116.8 2023.24
#Mann= 3 ,-1 , 0
  4700.8      .1       0  5001.5     .05       0  5005.5      .1       0
Bank Sta=5001.5,5005.5
XS Rating Curve= 0 ,0
Exp/Cntr=0.3,0.1

Type RM Length L Ch R = 1 ,36023   ,482,482,482
BEGIN DESCRIPTION:
Indian Creek 03 75.0
END DESCRIPTION:
XS GIS Cut Line= 3
      1882658.74     13917101.83        1883025.       13917125.
      1883324.97       13917175.
#Sta/Elev= 30
  4633.1  2035.3  4687.1 2029.15  4697.8 2026.66  4734.6 2023.12  4765.2 2018.65
  4804.3 2015.94    4859 2009.97  4912.7 2005.44  4951.6 1998.76  4960.5 1998.43
  4981.7 1994.24  4988.7 1990.58  4988.9 1990.08  4992.7 1990.58  5005.8 1991.76
    5016  1991.4  5051.4 1993.18  5065.5  1994.9  5078.8  1997.6  5084.9 1997.83
  5107.2 2003.15  5127.4 2006.65  5136.6 2010.14  5148.7 2013.14  5151.8 2014.94
  5191.3 2024.37  5206.3 2029.45    5240 2037.81  5297.5 2048.27  5304.2 2048.66
#Mann= 3 ,-1 , 0
  4633.1      .1       0  4988.7     .05       0  4992.7      .1       0
Bank Sta=4988.7,4992.7
XS Rating Curve= 0 ,0
Exp/Cntr=0.3,0.1

Type RM Length L Ch R = 1 ,35541   ,466,466,466
BEGIN DESCRIPTION:
Indian Creek 03 74.0
END DESCRIPTION:
XS GIS Cut Line= 3
      1882680.98     13917521.54        1883025.       13917575.
      1883224.96       13917575.
#Sta/Elev= 30
  4647.2 2012.97    4658 2011.29  4715.6  2006.9  4721.7 2007.07    4743  2005.4
  4758.2 2005.46  4773.3 2003.79  4776.4 2004.13  4809.8 1999.56  4840.1 1998.56
  4853.9 1996.02  4895.7 1993.25  4911.5 1991.57  4919.1 1990.02  4934.2 1989.08
  4940.3 1987.42    4964  1984.1  4970.7 1982.15  4976.7 1979.34    5007 1980.23
    5017 1979.27  5017.2 1978.77    5021 1979.27    5028 1980.64    5043 1987.43
  5075.3 1995.22    5106 2004.62  5139.6 2017.66  5154.6 2022.76  5195.3 2032.51
#Mann= 3 ,-1 , 0
  4647.2      .1       0    5017     .05       0    5021      .1       0
Bank Sta=5017,5021
XS Rating Curve= 0 ,0
Exp/Cntr=0.3,0.1

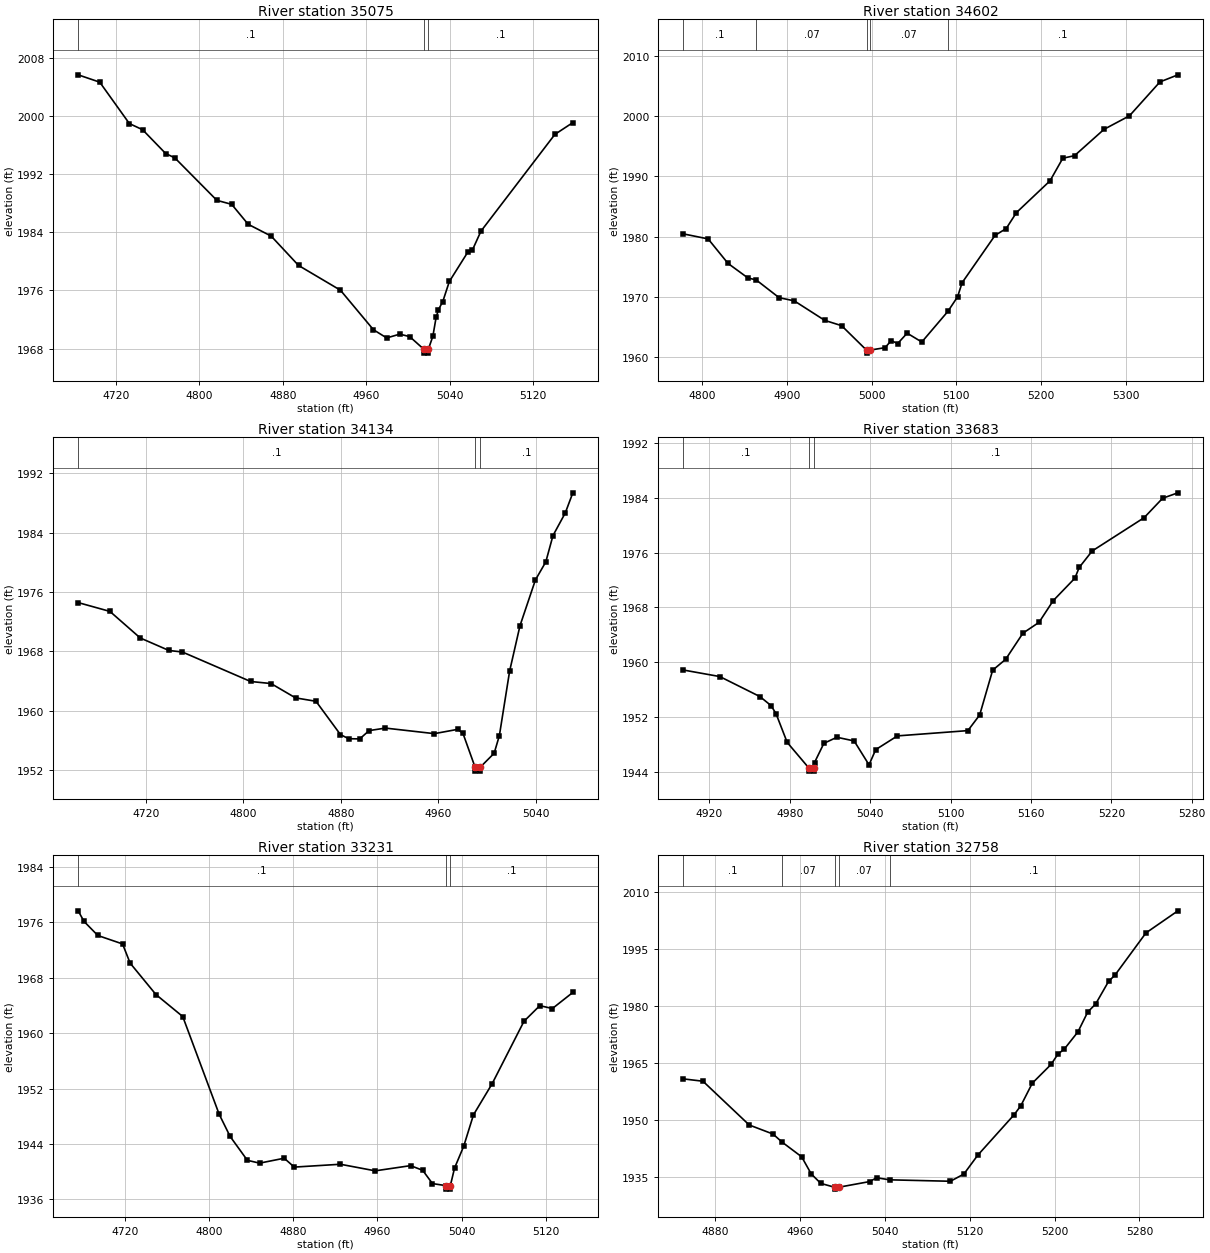
Type RM Length L Ch R = 1 ,35075   ,473,473,473
BEGIN DESCRIPTION:
Indian Creek 03 73.0
END DESCRIPTION:
XS GIS Cut Line= 3
        1882675.       13917925.        1882975.       13918025.
      1883124.97     13917975.01
#Sta/Elev= 30
  4683.8 2005.64  4704.5 2004.63  4732.9 1998.94  4745.6 1998.09  4767.7 1994.82
  4776.5 1994.22  4816.8 1988.38    4831 1987.83  4846.8 1985.09  4868.9 1983.46
  4895.1 1979.43  4935.3 1976.02  4966.9 1970.59  4979.6 1969.46  4992.2 1969.98
  5001.7 1969.64  5015.5 1967.87  5015.8 1967.37  5019.3 1967.37  5019.5 1967.87
  5023.9 1969.69    5027 1972.27  5029.3 1973.36  5033.4 1974.46  5039.7 1977.22
  5057.7 1981.33  5061.8 1981.54    5070 1984.14  5140.9 1997.45  5158.1 1999.07
#Mann= 3 ,-1 , 0
  4683.8      .1       0  5015.5     .05       0  5019.5      .1       0
Bank Sta=5015.5,5019.5
XS Rating Curve= 0 ,0
Exp/Cntr=0.3,0.1

Type RM Length L Ch R = 1 ,34602   ,468,468,468
BEGIN DESCRIPTION:
Indian Creek 03 72.0
END DESCRIPTION:
XS GIS Cut Line= 3
      1883025.01     13918624.98        1883125.       13918425.
      1883324.98     13918125.03
#Sta/Elev= 30
  4777.5 1980.45  4806.9 1979.61  4830.4 1975.53  4853.9 1973.11  4863.6 1972.79
  4890.7 1969.83  4908.6  1969.3  4944.6 1966.05  4964.5 1965.17  4993.9  1961.1
  4994.1  1960.6  4997.9  1961.1  5015.9 1961.51  5023.1  1962.7  5030.6 1962.18
  5041.9 1963.92  5059.2 1962.45  5089.9 1967.53  5101.4 1969.96  5106.8 1972.32
  5145.7  1980.2  5158.8 1981.33    5171    1984  5210.6 1989.28  5225.7 1993.04
  5239.5 1993.46  5274.4 1997.85  5304.4  2000.1  5340.4 2005.74  5361.6 2006.92
#Mann= 5 ,-1 , 0
  4777.5      .1       0  4863.6     .07       0  4993.9     .05       0
  4997.9     .07       0  5089.9      .1       0
Bank Sta=4993.9,4997.9
XS Rating Curve= 0 ,0
Exp/Cntr=0.3,0.1

Type RM Length L Ch R = 1 ,34134   ,451,451,451
BEGIN DESCRIPTION:
Indian Creek 03 71.0
END DESCRIPTION:
XS GIS Cut Line= 3
      1883224.97     13918675.01        1883525.       13918525.
      1883575.03     13918474.97
#Sta/Elev= 30
  4664.3 1974.57  4690.4 1973.38  4715.3  1969.8  4738.8 1968.12  4749.9 1967.91
  4805.9 1963.94  4822.7 1963.66  4842.8 1961.73  4859.6 1961.27  4879.7 1956.78
  4886.4 1956.23  4895.5  1956.2  4903.2 1957.32  4916.6 1957.66  4956.8 1956.91
    4976 1957.49  4980.3 1956.94  4990.3 1952.36  4990.5 1951.86    4994 1951.86
  4994.3 1952.36  5005.9 1954.27  5010.2 1956.66  5018.6 1965.34  5027.1 1971.45
  5039.8 1977.63  5048.3 1980.05  5054.2  1983.6  5064.3 1986.65  5070.5 1989.36
#Mann= 3 ,-1 , 0
  4664.3      .1       0  4990.3     .05       0  4994.3      .1       0
Bank Sta=4990.3,4994.3
XS Rating Curve= 0 ,0
Exp/Cntr=0.3,0.1

Type RM Length L Ch R = 1 ,33683   ,452,452,452
BEGIN DESCRIPTION:
Indian Creek 03 70.0
END DESCRIPTION:
XS GIS Cut Line= 3
        1883475.       13918925.        1883575.       13918925.
      1883825.04     13919025.02
#Sta/Elev= 30
  4900.4 1958.84  4927.7 1957.88  4957.7 1954.95    4966 1953.63  4969.7 1952.45
    4978 1948.26    4994 1944.56  4994.3 1944.06  4997.8 1944.06    4998 1944.56
  4998.4 1945.31  5005.4 1948.12  5015.1 1949.01    5028 1948.47  5039.1 1944.98
  5044.1  1947.2  5060.3 1949.21  5112.9 1949.98  5121.7 1952.26  5131.4 1958.81
  5141.1  1960.4    5154 1964.22    5166  1965.8  5176.6 1968.97  5192.8 1972.26
    5196 1973.82  5205.7 1976.23  5244.5  1981.1  5258.3 1983.94  5269.7 1984.73
#Mann= 3 ,-1 , 0
  4900.4      .1       0    4994     .05       0    4998      .1       0
Bank Sta=4994,4998
XS Rating Curve= 0 ,0
Exp/Cntr=0.3,0.1

Type RM Length L Ch R = 1 ,33231   ,473,473,473
BEGIN DESCRIPTION:
Indian Creek 03 69.0
END DESCRIPTION:
XS GIS Cut Line= 3
      1883175.02     13919524.98        1883425.       13919325.
      1883574.97       13919325.
#Sta/Elev= 30
  4675.6 1977.66  4681.2 1976.13  4694.3  1974.1  4717.8 1972.88    4725 1970.11
  4749.5 1965.58    4775  1962.4  4809.6  1948.3    4820  1945.1  4836.4 1941.65
    4848 1941.24  4871.4 1941.95    4881 1940.67  4924.8 1941.08  4957.9 1940.13
  4991.5 1940.88    5003 1940.21  5012.3 1938.29  5025.3 1937.99  5025.6 1937.49
  5029.1 1937.49  5029.3 1937.99  5033.3 1940.53    5042 1943.68  5051.3 1948.22
    5069  1952.7  5099.3 1961.72  5114.3 1963.97  5126.3 1963.56  5145.7 1965.88
#Mann= 3 ,-1 , 0
  4675.6      .1       0  5025.3     .05       0  5029.3      .1       0
Bank Sta=5025.3,5029.3
XS Rating Curve= 0 ,0
Exp/Cntr=0.3,0.1

Type RM Length L Ch R = 1 ,32758   ,446,446,446
BEGIN DESCRIPTION:
Indian Creek 03 68.0
END DESCRIPTION:
XS GIS Cut Line= 3
      1883375.04       13919725.        1883525.       13919725.
      1883825.01       13919625.
#Sta/Elev= 30
  4850.1 1960.82  4868.7  1960.2  4912.3 1948.68  4934.7  1946.3  4943.2 1944.19
  4961.7 1940.31  4970.7 1935.82  4979.7 1933.31  4992.7  1932.3  4992.9  1931.8
  4996.7  1932.3    5026  1933.8  5032.3  1934.8  5044.5 1934.25  5101.9 1933.87
  5114.6 1935.77  5127.7 1940.74    5162  1951.4  5168.3 1953.77  5179.1  1959.7
  5196.8 1964.63  5203.1 1967.29  5209.4 1968.72  5222.1  1973.2  5231.3  1978.4
  5238.8 1980.54    5251  1986.5  5256.9  1988.1  5286.2 1999.24  5316.3 2005.05
#Mann= 5 ,-1 , 0
  4850.1      .1       0  4943.2     .07       0  4992.7     .05       0
  4996.7     .07       0  5044.5      .1       0
Bank Sta=4992.7,4996.7
XS Rating Curve= 0 ,0
Exp/Cntr=0.3,0.1

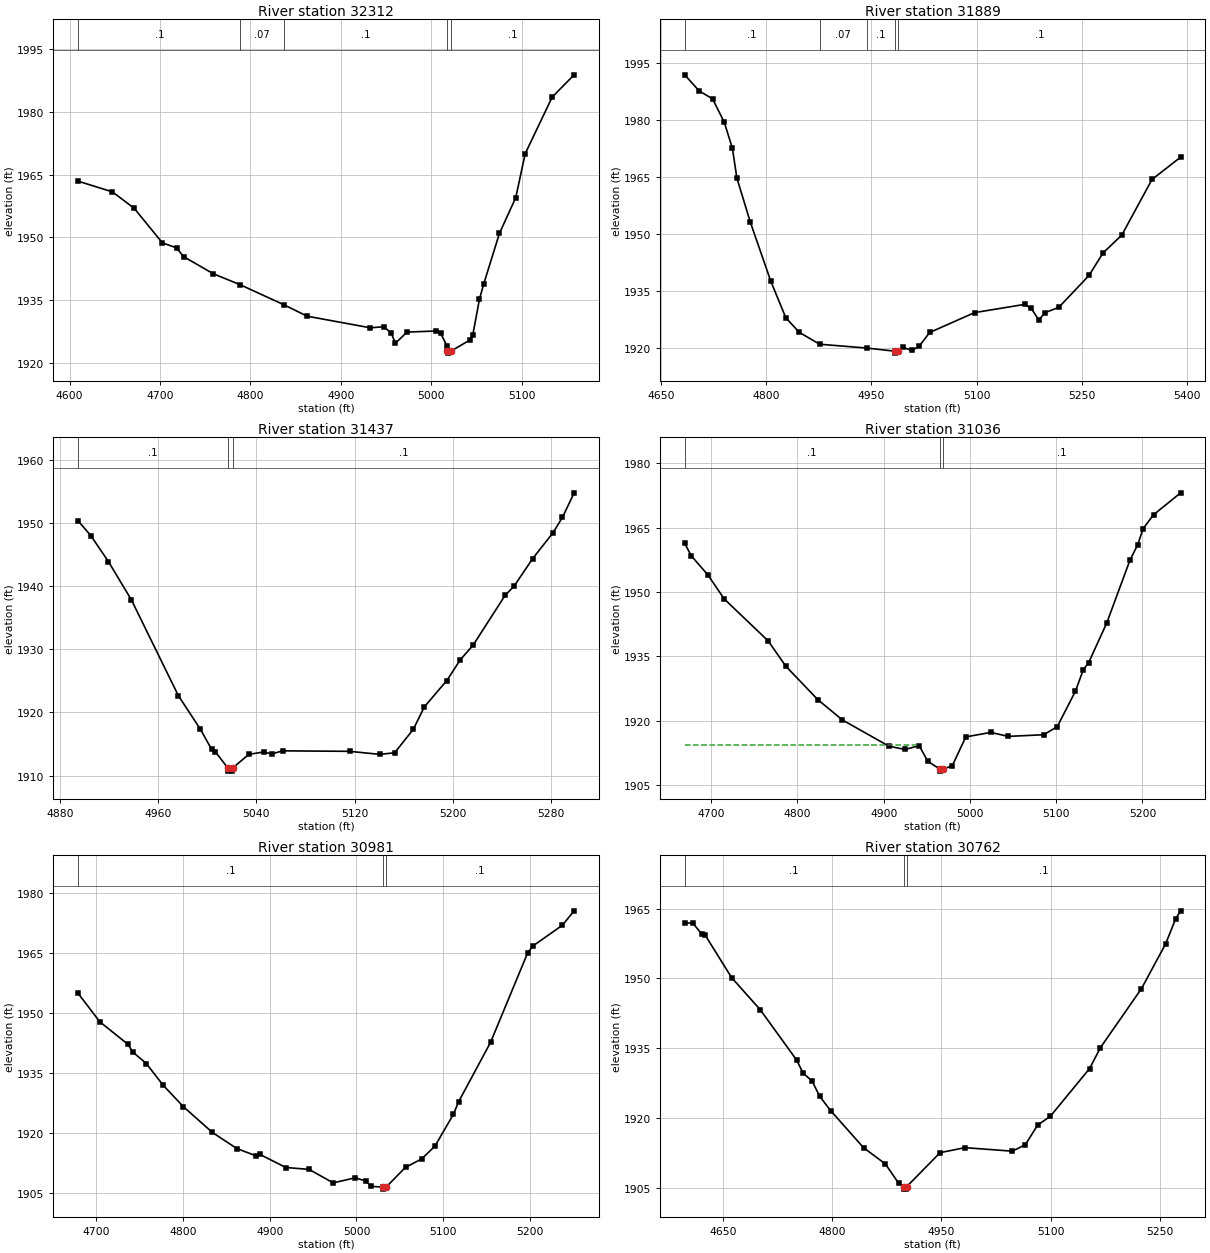
Type RM Length L Ch R = 1 ,32312   ,423,423,423
BEGIN DESCRIPTION:
Indian Creek 03 67.0
END DESCRIPTION:
XS GIS Cut Line= 3
      1883325.04     13919775.03        1883625.       13920025.
      1883775.02     13920075.01
#Sta/Elev= 30
  4609.5 1963.41  4647.3 1960.87  4671.4 1956.95  4702.6  1948.7  4718.3  1947.5
    4726 1945.42  4758.8 1941.34  4788.8  1938.7  4837.2 1933.91  4862.8  1931.2
  4932.7 1928.43  4947.6 1928.69  4955.7 1927.18  4960.4 1924.75  4973.2 1927.41
  5005.2 1927.67  5010.4 1927.16  5017.6 1924.01  5017.9 1922.89  5018.2 1922.39
  5021.9 1922.89  5043.1 1925.55    5046 1926.75  5053.3 1935.22  5057.9 1938.78
  5075.5 1950.99  5093.5 1959.49  5103.9 1969.96  5133.8 1983.48  5158.1 1988.79
#Mann= 5 ,-1 , 0
  4609.5      .1       0  4788.8     .07       0  4837.2      .1       0
  5017.9     .05       0  5021.9      .1       0
Bank Sta=5017.9,5021.9
XS Rating Curve= 0 ,0
Exp/Cntr=0.3,0.1

Type RM Length L Ch R = 1 ,31889   ,452,452,452
BEGIN DESCRIPTION:
Indian Creek 03 66.0
END DESCRIPTION:
XS GIS Cut Line= 3
        1882975.       13920125.        1883275.       13920225.
      1883574.97     13920474.97
#Sta/Elev= 30
  4683.8 1991.96  4704.5 1987.72  4723.5 1985.64  4740.1 1979.53  4751.8 1972.64
  4758.2 1964.79  4777.2 1953.28  4806.5 1937.65  4827.8 1928.09  4846.8 1924.23
  4876.2 1921.07  4942.9 1920.07  4983.9 1919.23  4984.2 1918.73  4987.9 1919.23
  4995.4 1920.23  5007.3 1919.43    5018 1920.56  5032.9 1924.16  5096.8 1929.39
  5168.2 1931.55  5177.7 1930.48  5188.4 1927.46  5197.4 1929.39  5216.9 1930.77
  5259.9 1939.16    5280  1945.1  5306.7 1949.79  5349.7 1964.42  5390.5  1970.3
#Mann= 5 ,-1 , 0
  4683.8      .1       0  4876.2     .07       0  4942.9      .1       0
  4983.9     .05       0  4987.9      .1       0
Bank Sta=4983.9,4987.9
XS Rating Curve= 0 ,0
Exp/Cntr=0.3,0.1

Type RM Length L Ch R = 1 ,31437   ,401,401,401
BEGIN DESCRIPTION:
Indian Creek 03 65.0
END DESCRIPTION:
XS GIS Cut Line= 3
      1883075.01       13920575.        1883175.       13920575.
      1883474.97       13920625.
#Sta/Elev= 30
  4894.8 1950.29  4905.1 1947.96  4919.4 1943.87  4938.1 1937.82  4976.4 1922.66
  4994.4 1917.33  5003.5 1914.16  5006.6 1913.77  5016.7 1911.22    5017 1910.72
  5020.5 1910.72  5020.7 1911.22  5033.7 1913.36  5046.1 1913.76  5052.4 1913.43
  5061.3 1913.93  5116.1 1913.85  5140.4 1913.37  5152.6 1913.62  5167.8 1917.32
  5176.9  1920.9  5195.1 1925.04  5206.2 1928.35  5216.6 1930.65  5242.7 1938.54
  5249.9 1939.96  5265.1 1944.34  5281.8 1948.46  5289.4 1950.87  5298.9 1954.74
#Mann= 3 ,-1 , 0
  4894.8      .1       0  5016.7     .05       0  5020.7      .1       0
Bank Sta=5016.7,5020.7
XS Rating Curve= 0 ,0
Exp/Cntr=0.3,0.1

Type RM Length L Ch R = 1 ,31036   ,55,55,55
BEGIN DESCRIPTION:
Indian Creek 03 64.1
END DESCRIPTION:
XS GIS Cut Line= 5
      1883011.38     13920816.99      1883289.17     13920916.82
      1883364.04     13920923.33      1883412.87     13920937.44
      1883565.85     13920921.16
#Sta/Elev= 30
  4669.2 1961.34  4676.9 1958.42    4696 1954.02  4715.1 1948.38  4766.1 1938.59
  4786.4 1932.74  4823.5 1924.94    4852 1920.21    4906 1914.09  4924.7 1913.32
  4941.1 1914.21    4951 1910.59  4964.8 1908.78  4965.1 1908.28  4968.8 1908.78
  4979.4 1909.49  4995.1 1916.25  5024.1  1917.3  5044.3 1916.37  5085.5 1916.76
  5101.2 1918.65  5122.3 1926.92  5131.3 1931.87  5137.6 1933.57  5158.5 1942.77
  5185.6  1957.5  5194.5 1961.03  5200.7 1964.76  5212.8    1968  5244.2 1973.11
#Mann= 3 ,-1 , 0
  4669.2      .1       0  4964.8     .05       0  4968.8      .1       0
#XS Ineff= 2 , 0
         4938.38 1914.29
Permanent Ineff=
       F       F
Bank Sta=4964.8,4968.8
XS Rating Curve= 0 ,0
Exp/Cntr=0.3,0.1

Type RM Length L Ch R = 1 ,30981   ,219,219,219
BEGIN DESCRIPTION:
Indian Creek 03 64.0
END DESCRIPTION:
XS GIS Cut Line= 3
      1883024.99       13920875.        1883325.       13920975.
      1883575.01       13920925.
#Sta/Elev= 30
  4679.5 1954.93  4704.4 1947.85  4736.6 1942.25  4742.4 1940.28    4758  1937.4
  4777.1 1932.03  4800.7  1926.6  4834.1 1920.16  4862.3 1916.13  4883.7 1914.37
  4888.4 1914.71  4918.7  1911.4  4945.4 1910.93  4973.2 1907.55  4998.4 1908.82
  5010.7 1908.03  5016.8  1906.7  5030.1 1906.49  5030.3 1905.99  5034.1 1906.49
  5056.5 1911.46  5074.9 1913.51  5090.4 1916.75  5111.6  1924.7  5117.7 1927.88
  5154.4  1942.7  5197.3 1965.17  5203.4 1966.85    5237 1971.98  5250.7 1975.61
#Mann= 3 ,-1 , 0
  4679.5      .1       0  5030.1     .05       0  5034.1      .1       0
Bank Sta=5030.1,5034.1
XS Rating Curve= 0 ,0
Exp/Cntr=0.3,0.1

Type RM Length L Ch R = 1 ,30762   ,235,235,235
BEGIN DESCRIPTION:
Indian Creek 03 63.1
END DESCRIPTION:
XS GIS Cut Line= 4
      1882961.45     13920982.77      1883138.56     13921144.25
      1883367.73     13921149.46       1883552.6     13921045.31
#Sta/Elev= 30
  4597.4 1961.94  4608.8 1961.84    4621 1959.48  4625.7 1959.25  4661.8 1950.17
  4701.1 1943.27    4751 1932.48    4760 1929.65  4772.4 1927.92  4782.9 1924.62
  4797.8 1921.58  4843.1  1913.6  4873.1  1910.1  4891.3 1905.95  4898.1  1905.2
  4898.4  1904.7  4901.9  1904.7  4902.1  1905.2  4948.2 1912.54  4982.3 1913.61
  5047.2 1912.86  5065.2 1914.23  5082.2 1918.48  5099.5 1920.34  5153.5 1930.62
  5168.3 1935.09  5224.7 1947.78  5257.9  1957.4  5271.6 1962.77  5278.5 1964.51
#Mann= 3 ,-1 , 0
  4597.4      .1       0  4898.1     .05       0  4902.1      .1       0
Bank Sta=4898.1,4902.1
XS Rating Curve= 0 ,0
Exp/Cntr=0.3,0.1

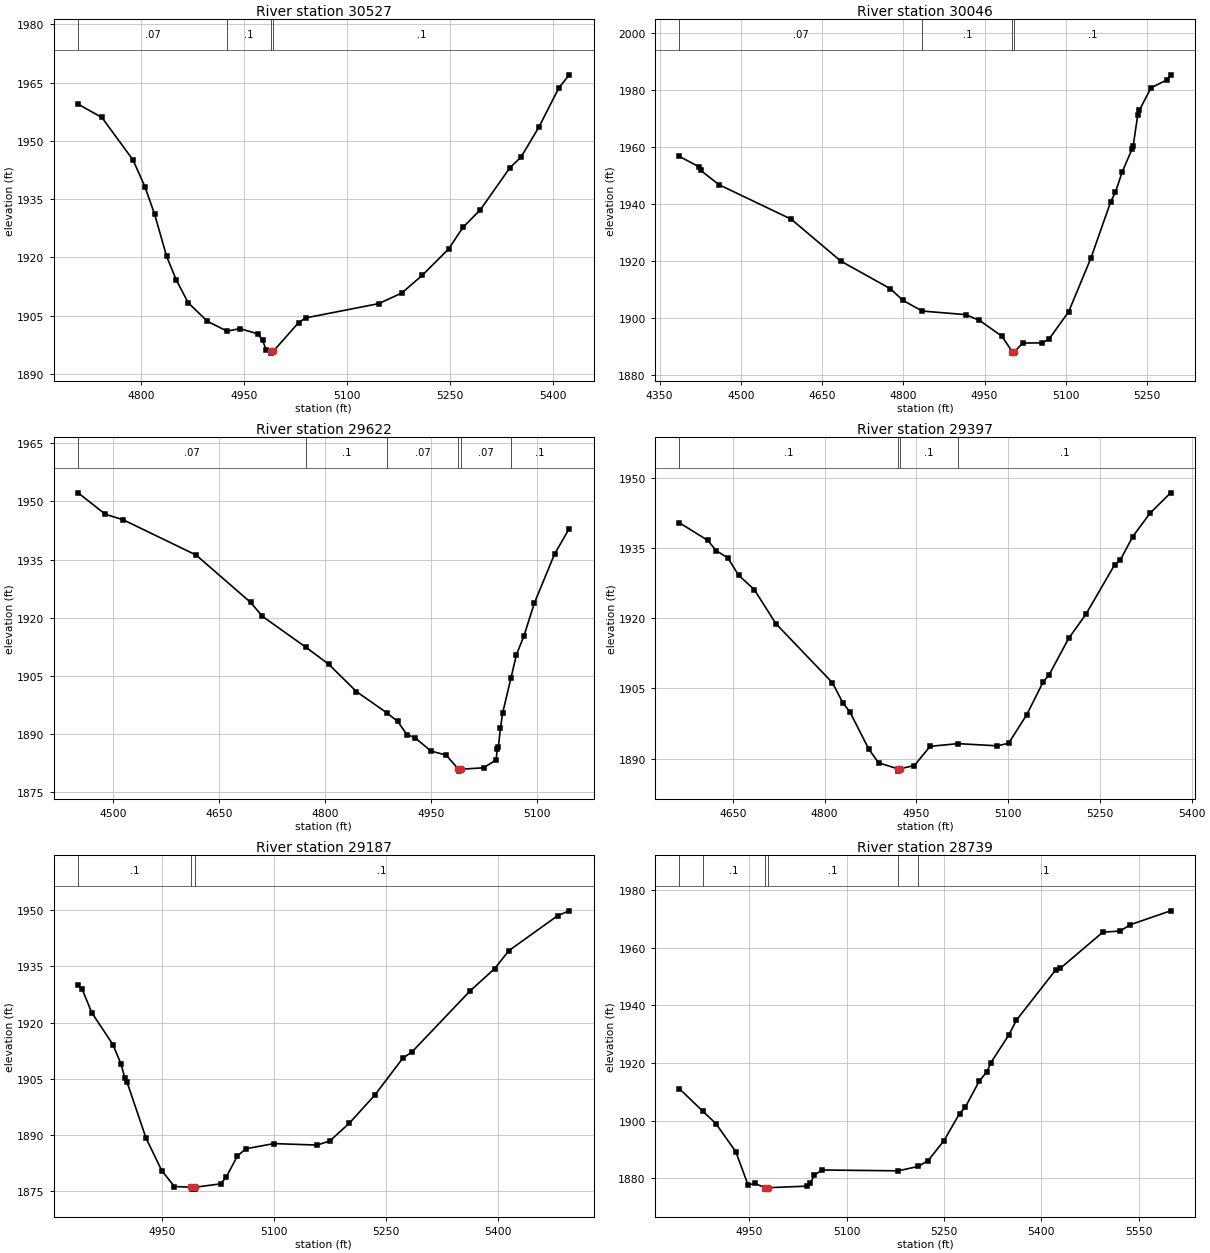
Type RM Length L Ch R = 1 ,30527   ,481,481,481
BEGIN DESCRIPTION:
Indian Creek 03 63.0
END DESCRIPTION:
XS GIS Cut Line= 3
      1883024.96     13921525.02        1883275.       13921375.
      1883575.03     13921074.97
#Sta/Elev= 30
  4708.5 1959.45  4743.1 1956.04  4788.6 1945.06  4806.1 1938.11  4820.1 1931.05
  4837.6 1920.22  4851.5 1914.21    4869 1908.29    4897 1903.53  4925.6 1900.99
  4944.4 1901.64  4970.5 1900.29  4977.5 1898.59  4982.6 1896.13  4989.1 1895.83
  4989.3 1895.33  4993.1 1895.83  5029.8 1903.17  5040.2  1904.4  5146.6 1908.08
  5180.2  1910.8  5210.3  1915.4  5248.5 1922.16  5269.3 1927.69  5294.8 1932.25
  5337.6 1943.02  5354.2 1945.84    5380 1953.51  5409.3 1963.67  5424.4 1967.01
#Mann= 4 ,-1 , 0
  4708.5     .07       0  4925.6      .1       0  4989.1     .05       0
  4993.1      .1       0
Bank Sta=4989.1,4993.1
XS Rating Curve= 0 ,0
Exp/Cntr=0.3,0.1

Type RM Length L Ch R = 1 ,30046   ,424,424,424
BEGIN DESCRIPTION:
Indian Creek 03 62.0
END DESCRIPTION:
XS GIS Cut Line= 3
      1883048.72     13921568.79      1883488.78     13921640.36
      1883824.99     13921325.01
#Sta/Elev= 30
  4386.7  1956.7  4423.1 1953.07  4425.7 1951.86  4459.5 1946.83    4593 1934.71
  4684.5 1920.03  4775.6 1910.38  4799.5 1906.23  4834.9  1902.5  4915.4 1901.24
  4940.6 1899.21  4981.8 1893.71  5001.2 1888.24  5001.4 1887.74  5005.2 1888.24
  5020.7 1891.29  5055.8 1891.32  5068.9 1892.64  5105.2 1902.23  5146.3 1921.05
  5182.9 1940.84  5191.7 1944.22  5203.9 1951.18  5222.4 1959.36  5224.4 1960.49
  5232.7 1971.08  5235.6 1972.84  5257.3 1980.79  5286.1 1983.51  5293.5 1985.34
#Mann= 4 ,-1 , 0
  4386.7     .07       0  4834.9      .1       0  5001.2     .05       0
  5005.2      .1       0
Bank Sta=5001.2,5005.2
XS Rating Curve= 0 ,0
Exp/Cntr=0.3,0.1

Type RM Length L Ch R = 1 ,29622   ,225,225,225
BEGIN DESCRIPTION:
Indian Creek 03 61.0
END DESCRIPTION:
XS GIS Cut Line= 3
      1883072.78     13921613.99        1883575.       13921825.
      1883724.96       13921825.
#Sta/Elev= 30
  4450.9 1952.23  4489.5 1946.68  4514.7 1945.26  4617.8 1936.15  4694.8 1923.93
  4711.7  1920.3  4773.2 1912.31  4805.4 1907.93  4844.5 1900.88  4888.1  1895.3
    4903 1893.14    4916 1889.74  4927.1 1888.98    4950  1885.5  4971.4 1884.45
  4988.9 1880.81  4989.1 1880.31  4992.9 1880.81  5024.3 1881.17  5042.3 1883.23
  5043.6 1886.02  5045.3 1886.54  5048.3 1891.45  5051.3 1895.29    5063 1904.28
  5070.9 1910.41  5081.3 1915.15  5096.3 1923.78  5124.9 1936.45  5145.6    1943
#Mann= 6 ,-1 , 0
  4450.9     .07       0  4773.2      .1       0  4888.1     .07       0
  4988.9     .05       0  4992.9     .07       0    5063      .1       0
Bank Sta=4988.9,4992.9
XS Rating Curve= 0 ,0
Exp/Cntr=0.3,0.1

Type RM Length L Ch R = 1 ,29397   ,210,210,210
BEGIN DESCRIPTION:
Indian Creek 03 60.1
END DESCRIPTION:
XS GIS Cut Line= 5
      1883146.13     13921740.12      1883458.64     13921999.46
      1883530.26     13922038.52       1883563.9     13922043.95
      1883751.62     13921834.52
#Sta/Elev= 30
  4562.6 1940.37  4608.8 1936.62  4622.9  1934.4  4641.7  1932.9  4659.2 1929.19
  4684.8 1926.13  4720.5  1918.8  4812.6 1906.24  4829.6 1901.98  4841.3 1899.98
  4872.2 1892.04  4888.1 1889.15  4919.2 1887.86  4919.5 1887.36  4923.2 1887.86
  4946.6 1888.56  4972.5 1892.65  5017.9 1893.23  5082.1 1892.76  5100.7  1893.3
  5130.4 1899.41  5157.4 1906.44  5166.5 1907.81  5198.9  1915.7  5227.1 1920.84
  5274.2 1931.44  5283.4 1932.44  5303.7 1937.44  5331.9 1942.41  5365.6 1946.77
#Mann= 4 ,-1 , 0
  4562.6      .1       0  4919.2     .05       0  4923.2      .1       0
  5017.9      .1       0
Bank Sta=4919.2,4923.2
XS Rating Curve= 0 ,0
Exp/Cntr=0.3,0.1

Type RM Length L Ch R = 1 ,29187   ,448,448,448
BEGIN DESCRIPTION:
Indian Creek 03 60.0
END DESCRIPTION:
XS GIS Cut Line= 3
        1883425.     13922374.99        1883475.       13922225.
        1883775.       13921825.
#Sta/Elev= 30
  4837.9 1929.91  4843.5 1928.81  4856.2 1922.63  4884.6 1914.11  4895.6 1908.83
  4900.5 1905.15  4903.6 1904.03  4928.9 1889.19  4950.1 1880.47  4966.9 1876.28
  4989.8 1876.08  4990.1 1875.58  4994.2 1875.58  4994.6 1876.08  5028.9 1876.99
  5036.4 1878.81  5051.4 1884.43  5062.7 1886.34  5100.2 1887.72  5158.1 1887.33
  5175.2 1888.43  5201.4 1893.18  5235.4 1900.64  5272.7 1910.43  5285.4 1912.19
  5362.7 1928.34    5396 1934.37  5415.2 1939.18  5480.4 1948.48    5496 1949.78
#Mann= 3 ,-1 , 0
  4837.9      .1       0  4989.8     .05       0  4994.6      .1       0
Bank Sta=4989.8,4994.6
XS Rating Curve= 0 ,0
Exp/Cntr=0.3,0.1

Type RM Length L Ch R = 1 ,28739   ,332,332,332
BEGIN DESCRIPTION:
Indian Creek 03 59.0
END DESCRIPTION:
XS GIS Cut Line= 3
      1883824.99     13922425.04        1883875.       13922275.
      1883949.78     13921680.84
#Sta/Elev= 30
  4842.3 1911.04  4878.7 1903.15  4898.5 1898.92  4929.2 1889.15  4948.1 1877.55
  4958.1 1878.15  4974.3 1876.66  4974.7 1876.16  4979.1 1876.66  5038.2 1877.19
  5044.2 1878.21  5050.2 1881.05  5062.3 1882.81  5179.5 1882.52  5210.3 1884.05
  5225.6 1886.09  5249.8 1892.95    5274 1902.42    5283 1904.69  5304.2 1913.63
  5316.3 1917.03  5322.3 1920.12  5349.8 1929.68  5361.6 1934.87  5422.1 1952.33
  5429.1 1952.87  5494.7 1965.44  5521.9 1965.88    5537 1968.05  5599.3 1972.88
#Mann= 6 ,-1 , 0
  4842.3     .07       0  4878.7      .1       0  4974.3     .05       0
  4979.1      .1       0  5179.5     .07       0  5210.3      .1       0
Bank Sta=4974.3,4979.1
XS Rating Curve= 0 ,0
Exp/Cntr=0.3,0.1

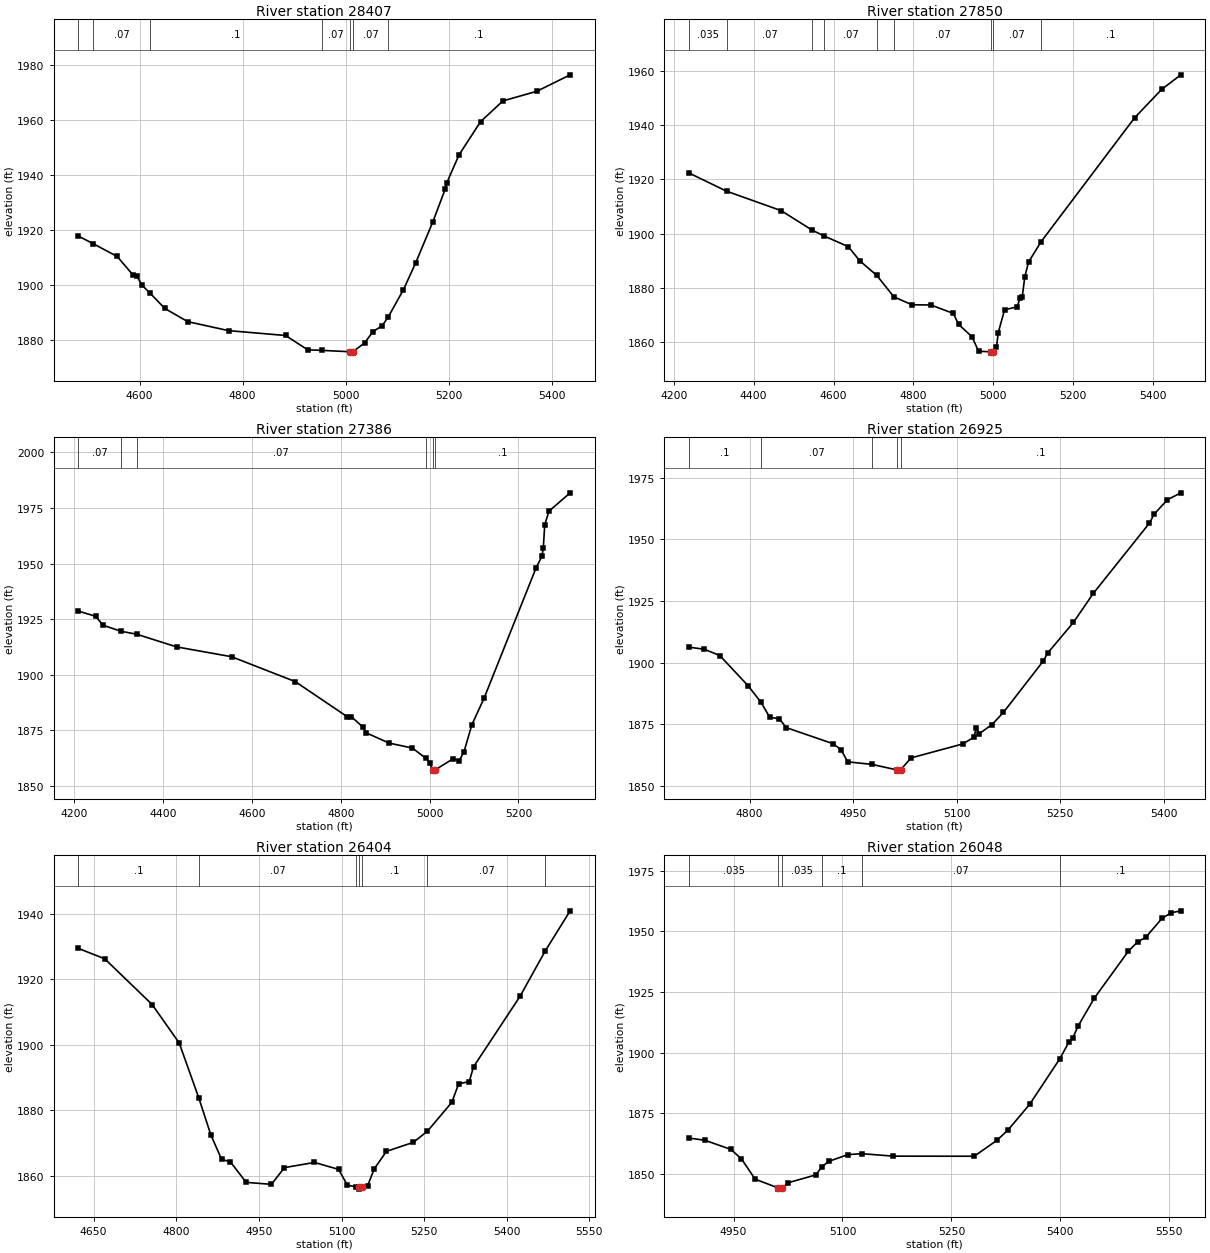
Type RM Length L Ch R = 1 ,28407   ,557,557,557
BEGIN DESCRIPTION:
Indian Creek 03 58.0
END DESCRIPTION:
XS GIS Cut Line= 4
      1883994.14      13922520.2      1884137.62      13922257.4
      1884026.37     13922041.15      1884047.14     13921629.28
#Sta/Elev= 30
  4480.9 1917.92  4510.3  1915.1  4556.7 1910.46  4587.5 1903.72  4594.3 1903.49
    4605    1900  4620.5 1897.13    4649 1891.59  4693.5 1886.78  4772.8 1883.51
  4883.5 1881.74  4926.4 1876.54  4954.5 1876.32  5009.3 1875.83  5009.7 1875.33
  5014.1 1875.83    5037 1879.06  5053.3 1883.18  5070.9 1885.25  5082.9 1888.52
  5112.1 1898.31  5136.2  1908.2  5169.2 1922.98  5193.2 1934.87  5196.2 1937.14
  5220.3 1947.44  5262.1 1959.49  5305.4 1967.02  5371.2 1970.51  5435.9  1976.5
#Mann= 7 ,-1 , 0
  4480.9    .035       0  4510.3     .07       0  4620.5      .1       0
  4954.5     .07       0  5009.3     .05       0  5014.1     .07       0
  5082.9      .1       0
Bank Sta=5009.3,5014.1
XS Rating Curve= 0 ,0
Exp/Cntr=0.3,0.1

Type RM Length L Ch R = 1 ,27850   ,464,464,464
BEGIN DESCRIPTION:
Indian Creek 03 57.0
END DESCRIPTION:
XS GIS Cut Line= 5
      1883990.34     13922579.18      1884316.96     13922353.52
        1884475.       13922025.        1884425.       13921875.
      1884317.87     13921582.14
#Sta/Elev= 30
  4237.6 1922.41    4332 1915.69    4469  1908.5  4546.5 1901.32  4577.1 1899.14
  4636.7 1895.27  4665.7 1890.04  4708.1 1884.68  4750.9 1876.79  4796.1 1873.87
  4843.7 1873.79  4899.7 1870.68  4912.9 1866.65  4946.3 1862.12  4962.9 1856.76
  4994.1 1856.57  4994.4 1856.07  4998.9 1856.57  5007.6 1858.18  5012.2 1863.62
    5028 1872.02  5059.6 1873.11  5066.9 1876.44  5072.3  1876.8  5078.6  1884.2
  5088.1 1889.64  5119.4 1897.09  5353.5 1942.71  5421.3 1953.16  5469.1 1958.51
#Mann= 9 ,-1 , 0
  4237.6    .035       0    4332     .07       0  4546.5      .1       0
  4577.1     .07       0  4708.1      .1       0  4750.9     .07       0
  4994.1     .05       0  4998.9     .07       0  5119.4      .1       0
Bank Sta=4994.1,4998.9
XS Rating Curve= 0 ,0
Exp/Cntr=0.3,0.1

Type RM Length L Ch R = 1 ,27386   ,461,461,461
BEGIN DESCRIPTION:
Indian Creek 03 56.0
END DESCRIPTION:
XS GIS Cut Line= 3
      1883945.02     13922630.95        1884675.       13922325.
      1884974.97     13922225.01
#Sta/Elev= 30
  4208.8 1928.62  4248.4 1926.22  4264.7 1922.22  4305.5 1919.48  4340.3 1918.18
  4430.6 1912.45  4554.2 1908.04  4697.4 1896.85  4814.5 1881.04  4824.2 1880.95
  4850.3  1876.3  4856.8 1873.81  4908.8 1869.15  4961.3 1866.91  4991.7 1862.29
  5000.3 1860.32  5006.8 1857.02  5007.2 1856.52    5012 1857.02  5053.7 1862.17
  5066.3 1861.12  5077.3 1865.11  5095.2 1877.41  5122.5 1889.26  5239.8 1948.06
  5252.9 1953.25    5256 1956.85  5259.2 1967.33  5268.7 1973.55  5316.5 1981.83
#Mann= 6 ,-1 , 0
  4208.8     .07       0  4305.5    .035       0  4340.3     .07       0
  4991.7      .1       0  5006.8     .05       0    5012      .1       0
Bank Sta=5006.8,5012
XS Rating Curve= 0 ,0
Exp/Cntr=0.3,0.1

Type RM Length L Ch R = 1 ,26925   ,521,521,521
BEGIN DESCRIPTION:
Indian Creek 03 55.0
END DESCRIPTION:
XS GIS Cut Line= 3
      1884575.02     13922924.98        1884775.       13922725.
      1885024.98     13922375.03
#Sta/Elev= 30
  4711.9  1906.3  4734.3 1905.45  4756.9 1902.88  4797.9  1890.6  4816.6 1883.89
    4829 1877.89  4843.2 1877.19  4853.1 1873.63    4921  1867.1  4932.3 1864.72
  4942.2 1859.74  4977.2 1858.72  5013.3 1856.48  5013.7 1855.98  5018.7 1856.48
    5034 1861.35  5108.5 1866.99  5124.8 1869.65  5128.5 1873.45  5132.8 1871.19
  5151.2 1874.87  5167.8 1879.82    5225 1900.47  5232.3 1904.03  5269.2 1916.33
  5297.9 1928.07  5379.4 1956.65  5386.1 1960.26  5405.5 1966.12  5424.8 1968.92
#Mann= 5 ,-1 , 0
  4711.9      .1       0  4816.6     .07       0  4977.2      .1       0
  5013.3     .05       0  5018.7      .1       0
Bank Sta=5013.3,5018.7
XS Rating Curve= 0 ,0
Exp/Cntr=0.3,0.1

Type RM Length L Ch R = 1 ,26404   ,356,356,356
BEGIN DESCRIPTION:
Indian Creek 03 55.1
END DESCRIPTION:
XS GIS Cut Line= 4
       1884713.9     13923340.79      1885014.26     13923120.29
      1885055.92     13923042.17      1885384.04     13922760.93
#Sta/Elev= 30
  4621.8 1929.41  4670.1 1926.21  4756.4 1912.22  4805.3 1900.54  4840.9 1883.77
  4862.8 1872.49  4882.2 1865.08  4898.3 1864.27  4926.9 1858.04  4972.7 1857.44
  4996.4 1862.54  5050.9 1864.12  5094.7 1861.99  5110.5 1857.21  5127.1 1856.62
    5131 1856.48  5131.4 1855.98  5136.4 1856.48  5147.5 1857.06  5159.5 1862.19
  5181.6  1867.5  5230.5 1870.25    5256 1873.65  5300.2 1882.43  5312.7 1888.12
  5331.8 1888.74  5339.7 1893.29  5424.1 1914.77  5470.2 1928.71  5515.1 1940.84
#Mann= 7 ,-1 , 0
  4621.8      .1       0  4840.9     .07       0  5127.1      .1       0
    5131     .05       0  5136.4      .1       0    5256     .07       0
  5470.2      .1       0
Bank Sta=5131,5136.4
XS Rating Curve= 0 ,0
Exp/Cntr=0.3,0.1

Type RM Length L Ch R = 1 ,26048   ,466,466,466
BEGIN DESCRIPTION:
Indian Creek 03 53.0
END DESCRIPTION:
XS GIS Cut Line= 3
      1885224.99     13923425.02        1885275.       13923325.
      1885674.99     13922925.01
#Sta/Elev= 30
  4888.4 1864.86  4910.6 1863.94  4946.2 1860.19  4960.9 1856.29  4979.7 1847.92
  5011.4 1844.31  5011.8 1843.81  5016.9 1844.31  5025.5 1846.46  5063.6 1849.71
  5071.6 1853.07    5082 1855.35  5107.5 1858.03  5126.7 1858.41  5169.7  1857.4
  5281.4 1857.36  5312.5 1863.87  5328.1 1868.21  5357.8 1878.77  5399.4 1897.57
  5412.2 1904.58  5417.2 1906.11  5424.3 1910.91  5446.9 1922.55  5493.6 1941.81
  5506.3 1945.63  5517.6 1947.56  5540.2 1955.43    5553 1957.69  5565.9 1958.47
#Mann= 6 ,-1 , 0
  4888.4    .035       0  5011.4    .035       0  5016.9    .035       0
  5071.6      .1       0  5126.7     .07       0  5399.4      .1       0
Bank Sta=5011.4,5016.9
XS Rating Curve= 0 ,0
Exp/Cntr=0.3,0.1