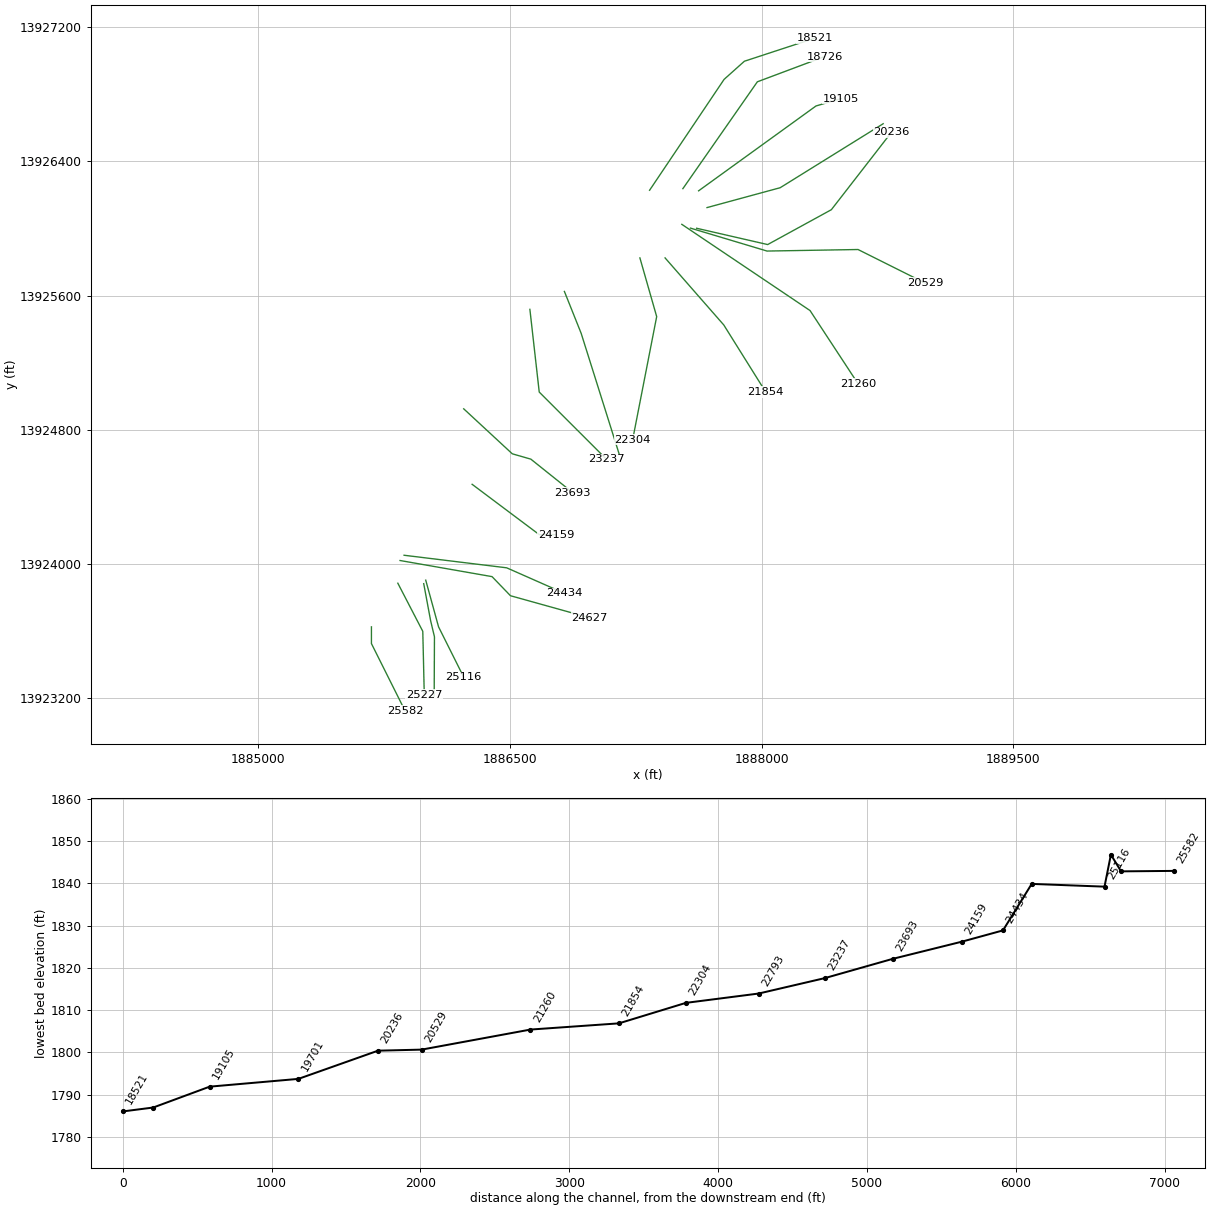
HEC-RAS study Indian Creek 03.prj: Indian Creek 03 Base Level Engineering

--- Indian Creek 03.g01 (geometry) --- (continued)

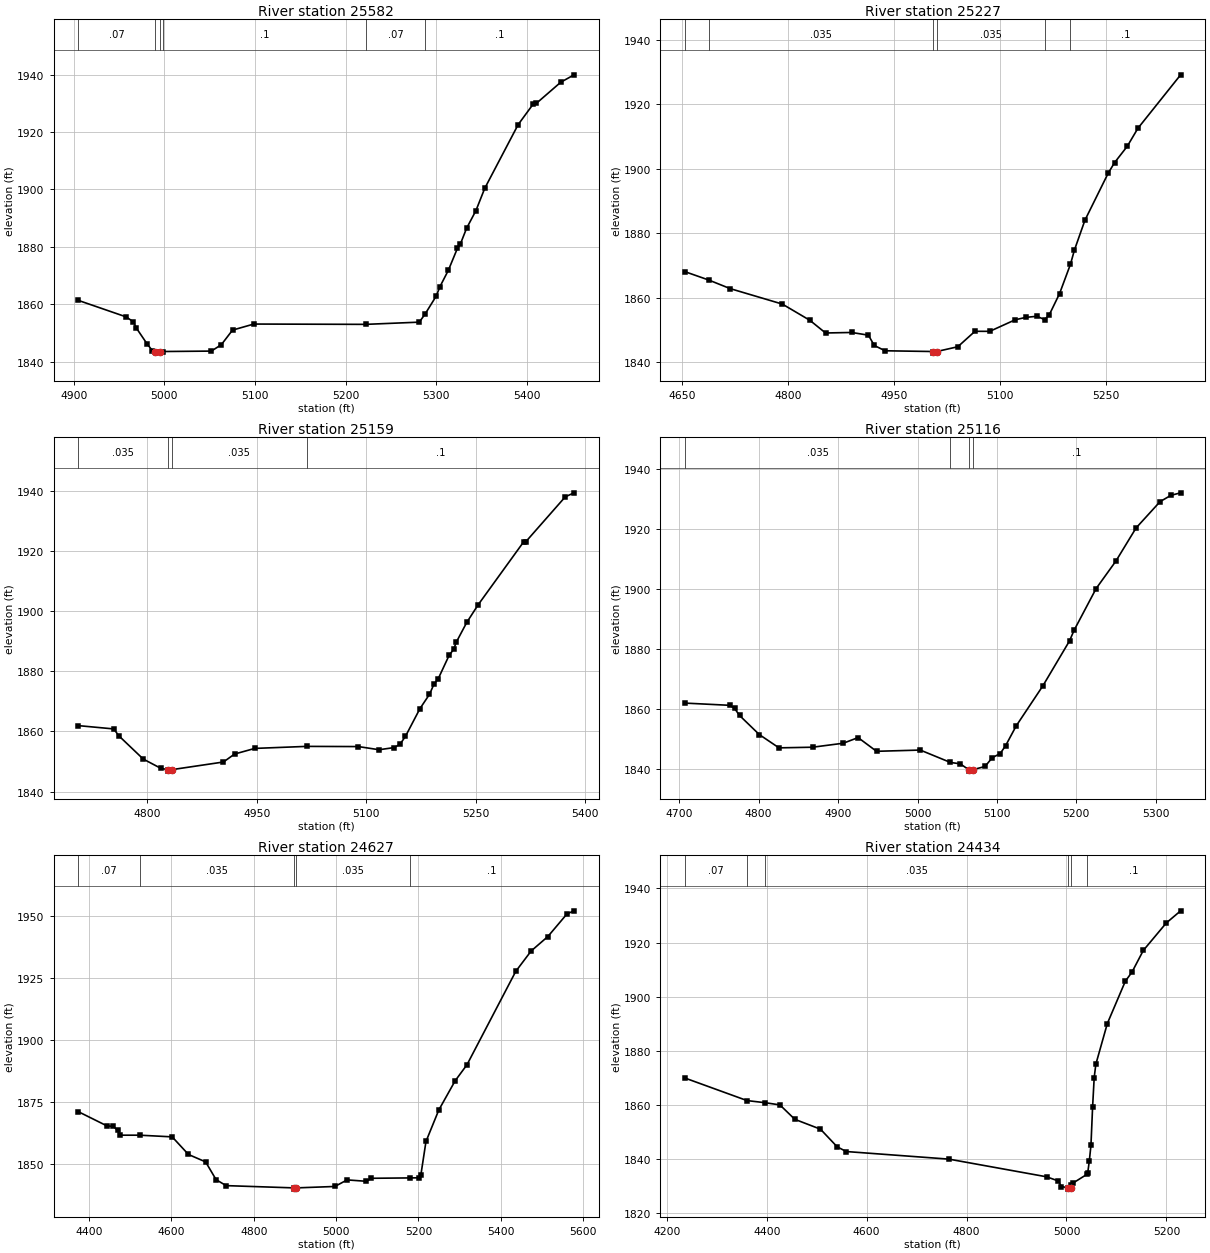
Type RM Length L Ch R = 1 ,25582   ,355,355,355
BEGIN DESCRIPTION:
Indian Creek 03 52.0
END DESCRIPTION:
XS GIS Cut Line= 3
        1885675.     13923624.97        1885675.       13923525.
      1885875.01     13923124.99
#Sta/Elev= 30
  4905.1 1861.32  4958.1 1855.55  4965.9 1853.82  4968.9  1851.8  4980.9 1846.21
  4986.9 1843.79  4990.1 1843.45  4990.6 1842.95  4995.7 1843.45  4998.7 1843.51
  5051.9 1843.66  5062.9 1845.87  5075.3 1850.97  5098.8 1853.08  5222.3 1852.97
  5281.4 1853.74  5287.7 1856.48  5300.1 1862.81  5304.3 1866.14  5313.5 1871.79
  5323.5 1879.43  5326.9 1881.04  5333.6  1886.4    5344 1892.62  5353.7 1900.36
  5390.6 1922.56  5407.4  1929.8  5410.7 1929.96  5437.6 1937.31  5452.3 1939.89
#Mann= 6 ,-1 , 0
  4905.1     .07       0  4990.1     .05       0  4995.7     .07       0
  4998.7      .1       0  5222.3     .07       0  5287.7      .1       0
Bank Sta=4990.1,4995.7
XS Rating Curve= 0 ,0
Exp/Cntr=0.3,0.1

Type RM Length L Ch R = 1 ,25227   ,68,68,68
BEGIN DESCRIPTION:
Indian Creek 03 51.2
END DESCRIPTION:
XS GIS Cut Line= 3
      1885832.22     13923885.25      1885981.04     13923598.18
      1885989.87     13923218.53
#Sta/Elev= 30
  4653.4 1868.12  4687.4 1865.51  4717.7 1862.85  4791.6 1858.06  4830.7 1853.02
  4852.9 1849.09    4890 1849.25  4913.7 1848.41    4922 1845.22  4937.3 1843.57
    5005 1843.34  5005.4 1842.84  5010.6 1843.34  5040.5 1844.82  5064.8 1849.61
  5085.8  1849.6  5121.8 1853.18  5136.8 1853.93  5152.5 1854.27  5163.5 1853.27
  5169.8 1854.55  5184.8 1861.31  5200.3 1870.44  5205.8 1874.77  5220.8 1884.09
  5253.8 1898.69  5262.8 1901.95  5280.8 1907.01  5295.9  1912.6  5356.5 1929.19
#Mann= 6 ,-1 , 0
  4653.4     .07       0  4687.4    .035       0    5005    .035       0
  5010.6    .035       0  5163.5     .07       0  5200.3      .1       0
Bank Sta=5005,5010.6
XS Rating Curve= 0 ,0
Exp/Cntr=0.3,0.1

Type RM Length L Ch R = 1 ,25159   ,43,43,43
BEGIN DESCRIPTION:
Indian Creek 03 51.1
END DESCRIPTION:
XS GIS Cut Line= 4
      1885986.55     13923882.54      1886027.53     13923662.57
      1886050.55     13923565.58      1886048.87     13923210.13
#Sta/Elev= 30
  4705.8 1861.93  4754.4 1860.83  4761.1 1858.58  4794.7 1850.82  4819.1  1847.7
  4828.5 1847.31    4829 1846.81  4834.1 1847.31  4904.5 1849.84  4919.8 1852.49
  4947.5 1854.36  5018.4 1855.03  5089.2 1854.97  5117.7 1853.92  5138.7 1854.65
  5146.5  1855.8  5153.7 1858.33  5173.6 1867.57  5186.7 1872.33  5192.7 1875.64
  5198.7 1877.53  5213.7 1885.35  5219.7 1887.23  5223.5 1889.71  5237.7 1896.21
  5253.3 1902.08  5315.7 1923.02  5318.7 1923.07  5372.7 1937.97  5384.7 1939.29
#Mann= 4 ,-1 , 0
  4705.8    .035       0  4828.5    .035       0  4834.1    .035       0
  5018.4      .1       0
Bank Sta=4828.5,4834.1
XS Rating Curve= 0 ,0
Exp/Cntr=0.3,0.1

Type RM Length L Ch R = 1 ,25116   ,489,489,489
BEGIN DESCRIPTION:
Indian Creek 03 51.0
END DESCRIPTION:
XS GIS Cut Line= 3
      1885998.57     13923903.48        1886075.       13923625.
      1886225.01     13923324.99
#Sta/Elev= 30
  4707.1  1861.9  4763.4 1861.16  4769.6 1860.15  4775.9 1857.78  4800.8 1851.41
  4825.6 1846.98  4867.9 1847.19  4906.5 1848.52  4925.2  1850.4  4948.4 1845.83
  5003.5 1846.24  5041.5 1842.11  5053.8 1841.66  5064.4 1839.72  5064.9 1839.22
    5070 1839.72    5085 1840.77  5094.1 1843.69  5104.1 1845.07  5110.9 1847.69
  5124.3 1854.31  5157.8 1867.63  5191.4 1882.63  5197.1 1886.15  5224.9 1900.08
  5249.8 1909.24  5275.2 1920.28  5305.4 1929.05  5319.1 1931.16  5331.3 1931.99
#Mann= 4 ,-1 , 0
  4707.1    .035       0  5041.5      .1       0  5064.4    .035       0
    5070      .1       0
Bank Sta=5064.4,5070
XS Rating Curve= 0 ,0
Exp/Cntr=0.3,0.1

Type RM Length L Ch R = 1 ,24627   ,193,193,193
BEGIN DESCRIPTION:
Mapping XS 1010cf1f
END DESCRIPTION:
XS GIS Cut Line= 4
      1885845.43     13924020.56       1886393.8     13923924.48
       1886503.6      13923810.6      1886974.15     13923679.44
#Sta/Elev= 30
  4374.3 1871.09  4443.7 1865.37    4459 1865.17    4470 1863.54  4475.2 1861.62
  4523.5 1861.61  4602.1 1860.94  4641.7 1853.83  4683.3 1850.85  4708.7 1843.69
  4733.1 1841.28  4897.8 1840.37  4898.2 1839.87  4903.5 1840.37    4997 1840.94
  5026.8 1843.59  5073.4 1843.03  5085.7 1844.24  5180.2 1844.39  5200.2 1844.43
  5205.7 1845.48  5218.2 1859.07  5249.3 1871.76    5289 1883.54  5317.8 1890.03
  5436.2 1927.67  5473.6 1935.89  5514.1  1941.7  5560.6 1950.84  5577.7 1952.06
#Mann= 5 ,-1 , 0
  4374.3     .07       0  4523.5    .035       0  4897.8    .035       0
  4903.5    .035       0  5180.2      .1       0
Bank Sta=4897.8,4903.5
XS Rating Curve= 0 ,0
Exp/Cntr=0.3,0.1

Type RM Length L Ch R = 1 ,24434   ,275,275,275
BEGIN DESCRIPTION:
Indian Creek 03 50.0
END DESCRIPTION:
XS GIS Cut Line= 3
      1885869.41     13924051.98      1886480.99     13923977.02
      1886825.03     13923824.98
#Sta/Elev= 30
  4236.2 1869.93  4360.6 1861.59  4397.4 1860.79  4426.4 1859.99  4456.3 1854.66
  4507.6 1851.02  4540.9 1844.53    4559 1842.76  4764.6 1839.95  4960.1 1833.42
  4983.4  1831.9    4990  1829.8  5003.3 1829.36  5003.8 1828.86  5009.3 1829.36
  5009.6 1830.53  5012.8 1831.07  5041.4 1834.38  5042.4 1834.66  5045.7 1839.23
    5049 1845.05  5052.3 1859.25  5055.5 1870.12  5058.8 1875.03  5081.8 1890.08
  5117.9 1905.74  5131.2  1909.1  5153.8 1917.09  5199.9 1927.26  5228.5 1931.73
#Mann= 6 ,-1 , 0
  4236.2     .07       0  4360.6      .1       0  4397.4    .035       0
  5003.3    .035       0  5009.3    .035       0  5041.4      .1       0
Bank Sta=5003.3,5009.3
XS Rating Curve= 0 ,0
Exp/Cntr=0.3,0.1

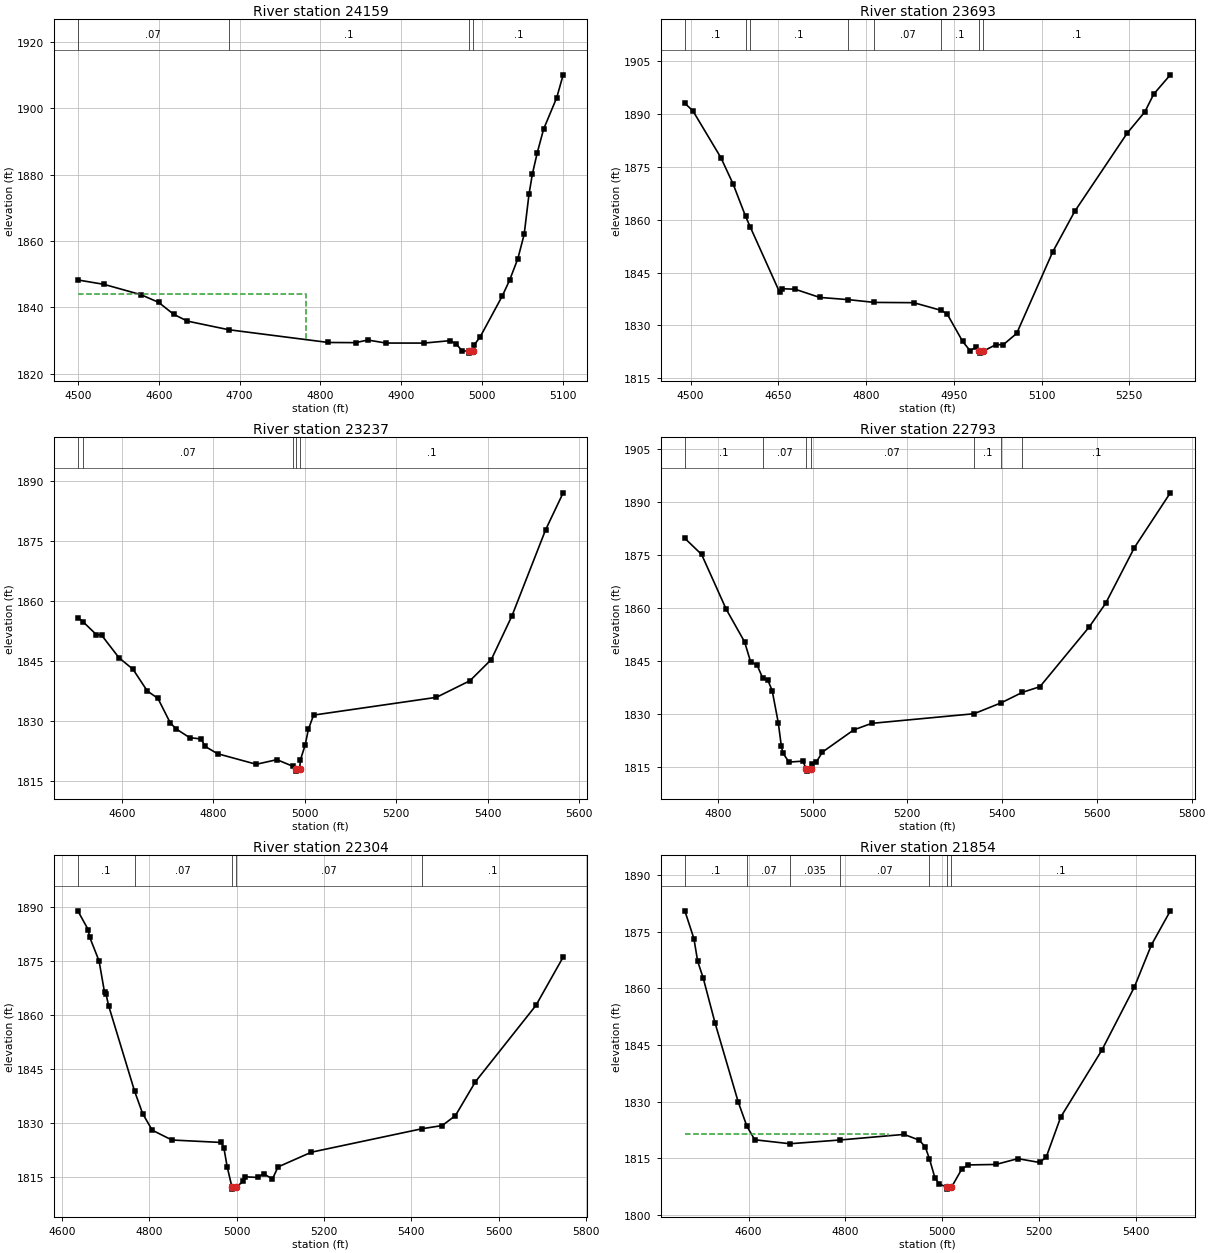
Type RM Length L Ch R = 1 ,24159   ,466,466,466
BEGIN DESCRIPTION:
Indian Creek 03 49.0
END DESCRIPTION:
XS GIS Cut Line= 3
      1886275.04     13924474.97        1886675.       13924175.
      1886775.04       13924175.
#Sta/Elev= 30
    4500 1848.27  4532.3 1846.95    4578 1843.83  4599.8 1841.53  4618.5 1837.91
  4635.4 1835.86  4686.5 1833.26  4809.8 1829.41  4843.5 1829.36  4858.5 1830.15
    4881 1829.24    4928 1829.23  4959.8 1829.95  4967.3 1829.08  4974.8 1826.99
    4983  1826.7  4983.5  1826.2    4989  1826.7  4989.8 1828.61  4997.3 1831.05
  5024.8 1843.46  5033.8 1848.21    5044 1854.71  5051.8 1862.03  5057.8 1874.19
    5062 1880.31    5068 1886.66  5075.8 1893.76    5092 1903.23    5100 1910.15
#Mann= 4 ,-1 , 0
    4500     .07       0  4686.5      .1       0    4983     .05       0
    4989      .1       0
#XS Ineff= 2 , 0
         4781.72 1843.95
Permanent Ineff=
       F       F
Bank Sta=4983,4989
XS Rating Curve= 0 ,0
Exp/Cntr=0.3,0.1

Type RM Length L Ch R = 1 ,23693   ,456,456,456
BEGIN DESCRIPTION:
Indian Creek 03 48.0
END DESCRIPTION:
XS GIS Cut Line= 4
      1886224.98     13924925.02       1886514.4     13924656.81
        1886625.       13924625.      1886874.98     13924425.01
#Sta/Elev= 30
  4490.3 1893.05  4503.7 1890.99  4551.7 1877.65  4572.5  1870.2  4593.9 1860.99
  4601.6 1858.06  4651.9 1839.49  4656.3 1840.41  4678.4 1840.29  4720.5 1837.95
  4768.7 1837.33  4814.1 1836.53  4881.4 1836.45  4927.8 1834.29  4938.3 1833.32
    4965 1825.45  4977.9 1822.77  4987.3  1823.8  4993.7 1822.62  4994.2 1822.12
  4999.7 1822.62  5022.1 1824.56  5034.3 1824.49  5057.4 1827.72  5118.9 1850.85
  5156.6 1862.39  5246.6 1884.68  5276.5 1890.66  5291.7 1895.72  5320.1 1901.19
#Mann= 8 ,-1 , 0
  4490.3      .1       0  4593.9     .07       0  4601.6      .1       0
  4768.7    .035       0  4814.1     .07       0  4927.8      .1       0
  4993.7     .05       0  4999.7      .1       0
Bank Sta=4993.7,4999.7
XS Rating Curve= 0 ,0
Exp/Cntr=0.3,0.1

Type RM Length L Ch R = 1 ,23237   ,444,444,444
BEGIN DESCRIPTION:
Indian Creek 03 47.0
END DESCRIPTION:
XS GIS Cut Line= 3
      1886619.33     13925518.16        1886675.       13925025.
      1887075.02     13924624.98
#Sta/Elev= 30
  4503.4 1855.88  4514.8 1854.83  4543.7 1851.65  4555.7 1851.45  4593.6 1845.83
  4624.2 1842.97  4655.4 1837.56  4678.7 1835.71  4705.9 1829.55  4718.8 1828.08
    4748 1825.92  4773.1 1825.58  4782.2 1823.71  4809.3  1821.9  4893.9 1819.27
  4939.1 1820.42  4973.7 1818.78  4980.1 1818.06  4980.6 1817.56  4988.7 1818.06
  4990.5 1820.37  5000.9 1824.09    5008 1828.03  5019.3 1831.54    5288 1835.97
  5361.5 1840.12  5408.2 1845.41  5453.4 1856.31    5527 1877.78  5565.4    1887
#Mann= 5 ,-1 , 0
  4503.4      .1       0  4514.8     .07       0  4973.7      .1       0
  4980.1     .05       0  4988.7      .1       0
Bank Sta=4980.1,4988.7
XS Rating Curve= 0 ,0
Exp/Cntr=0.3,0.1

Type RM Length L Ch R = 1 ,22793   ,489,489,489
BEGIN DESCRIPTION:
Indian Creek 03 46.0
END DESCRIPTION:
XS GIS Cut Line= 3
      1886825.01     13925624.97        1886925.       13925375.
      1887151.61     13924654.83
#Sta/Elev= 30
  4730.8 1879.78  4765.9 1875.25  4817.8 1859.74  4856.6  1850.5  4869.5 1844.75
  4882.5 1844.06  4894.9 1840.24  4905.1 1839.82  4914.8  1836.7  4927.7 1827.59
  4934.1 1821.01  4937.4 1819.03  4950.3 1816.47  4979.4 1816.74  4987.2 1814.41
  4987.7 1813.91  4995.8 1814.41  4998.8 1816.01  5008.2 1816.53  5020.8  1819.3
  5086.9 1825.58  5124.6 1827.43  5340.8 1830.16  5398.6 1833.28  5442.8 1836.22
  5479.8 1837.81  5583.8 1854.73  5618.4 1861.39  5679.2  1877.2    5755  1892.7
#Mann= 7 ,-1 , 0
  4730.8      .1       0  4894.9     .07       0  4987.2     .05       0
  4995.8     .07       0  5340.8      .1       0  5398.6     .07       0
  5442.8      .1       0
Bank Sta=4987.2,4995.8
XS Rating Curve= 0 ,0
Exp/Cntr=0.3,0.1

Type RM Length L Ch R = 1 ,22304   ,450,450,450
BEGIN DESCRIPTION:
Indian Creek 03 45.0
END DESCRIPTION:
XS GIS Cut Line= 3
      1887275.01     13925824.98        1887375.       13925475.
      1887231.81     13924741.02
#Sta/Elev= 30
  4636.1 1888.82  4659.8 1883.62    4663 1881.61  4684.8 1874.92  4697.3 1866.25
  4700.4 1865.91  4706.6 1862.56  4766.2 1838.83  4784.6 1832.64  4806.5 1828.04
  4851.6 1825.31  4965.1 1824.63  4970.7 1823.13  4978.2 1817.92  4989.3  1812.2
  4989.8  1811.7    4998  1812.2  5015.2 1813.86  5018.3 1815.12  5048.8 1814.93
  5061.5 1815.99  5081.9 1814.49  5094.7 1817.85  5171.1 1821.93  5424.4 1828.43
  5470.9 1829.32  5501.2 1832.09    5547 1841.47  5685.5 1862.61  5747.9    1876
#Mann= 5 ,-1 , 0
  4636.1      .1       0  4766.2     .07       0  4989.3     .05       0
    4998     .07       0  5424.4      .1       0
Bank Sta=4989.3,4998
XS Rating Curve= 0 ,0
Exp/Cntr=0.3,0.1

Type RM Length L Ch R = 1 ,21854   ,594,594,594
BEGIN DESCRIPTION:
Indian Creek 03 44.0
END DESCRIPTION:
XS GIS Cut Line= 3
      1887425.02     13925824.97        1887775.       13925425.
      1888025.02     13925024.98
#Sta/Elev= 30
  4468.5  1880.4  4486.9  1873.2  4494.8 1867.13  4506.2 1862.73  4530.7 1850.82
  4578.5 1829.94  4596.6 1823.45  4612.8 1819.91  4685.4 1818.87  4789.2 1819.86
  4921.4 1821.34  4952.7 1819.82  4965.2 1818.01  4973.8 1814.85  4985.1 1809.85
  4993.7 1808.24  5010.3 1807.35  5010.8 1806.85  5019.3 1807.35  5041.1 1812.26
  5054.4 1813.26    5111 1813.38  5156.6 1814.92  5201.6  1813.9  5215.3 1815.37
  5245.1 1825.92    5330 1843.61  5397.2  1860.3  5432.6 1871.51  5471.7 1880.53
#Mann= 7 ,-1 , 0
  4468.5      .1       0  4596.6     .07       0  4685.4    .035       0
  4789.2     .07       0  4973.8      .1       0  5010.3     .05       0
  5019.3      .1       0
#XS Ineff= 2 , 0
         4889.11 1821.56
Permanent Ineff=
       F       F
Bank Sta=5010.3,5019.3
XS Rating Curve= 0 ,0
Exp/Cntr=0.3,0.1

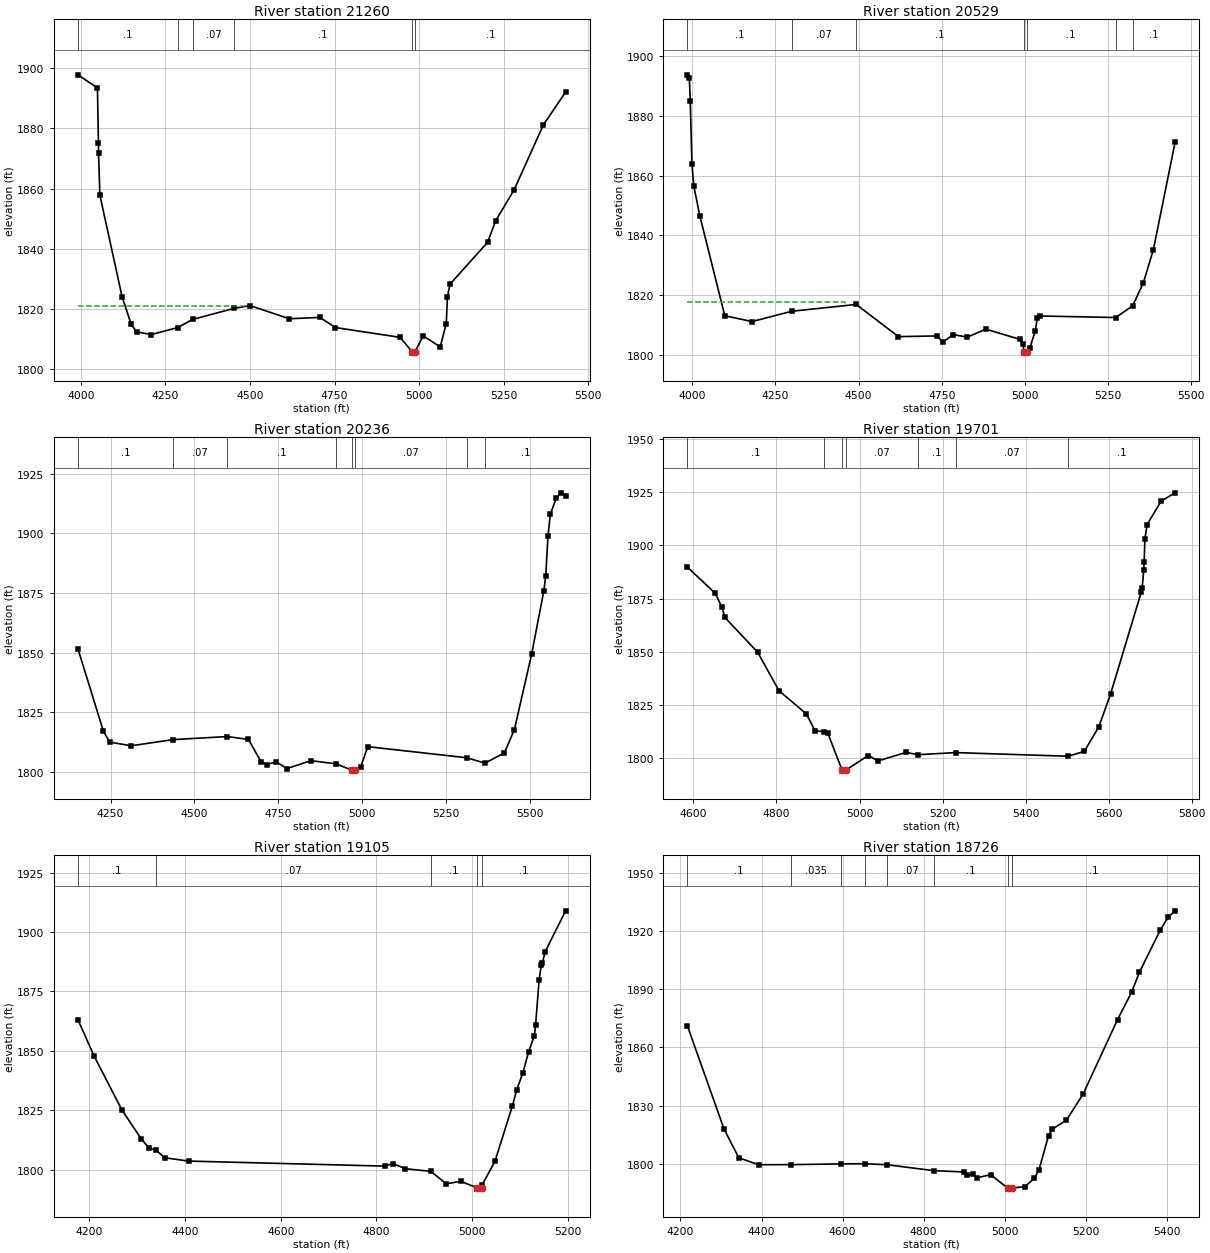
Type RM Length L Ch R = 1 ,21260   ,731,731,731
BEGIN DESCRIPTION:
Indian Creek 03 43.0
END DESCRIPTION:
XS GIS Cut Line= 3
      1887524.98     13926025.02      1888289.09     13925510.96
      1888575.01     13925074.99
#Sta/Elev= 30
  3991.1 1897.72  4048.8 1893.39  4051.8 1875.17  4052.1  1871.7    4056  1857.8
  4121.6 1824.13  4148.5 1814.97  4164.5 1812.45  4207.9 1811.53  4285.7 1813.85
  4330.1 1816.55  4453.9 1820.27  4500.7 1821.13  4616.4 1816.79  4706.8 1817.23
  4752.5 1813.87  4944.1 1810.61    4979 1805.88  4979.5 1805.38  4988.1 1805.88
  5012.3 1811.09  5062.5 1807.45  5080.4 1815.19    5084 1824.12  5091.2 1828.22
  5202.4 1842.11  5226.6 1849.31  5281.3 1859.62  5367.4 1881.08  5433.4 1892.01
#Mann= 6 ,-1 , 0
  3991.1      .1       0  4285.7    .035       0  4330.1     .07       0
  4453.9      .1       0    4979     .05       0  4988.1      .1       0
#XS Ineff= 2 , 0
         4488.71 1821.16
Permanent Ineff=
       F       F
Bank Sta=4979,4988.1
XS Rating Curve= 0 ,0
Exp/Cntr=0.3,0.1

Type RM Length L Ch R = 1 ,20529   ,293,293,293
BEGIN DESCRIPTION:
Indian Creek 03 42.0
END DESCRIPTION:
XS GIS Cut Line= 4
      1887576.09     13926002.68      1888032.76      13925865.8
        1888575.       13925875.      1888975.02     13925674.99
#Sta/Elev= 30
  3985.3 1893.65  3991.3 1892.45  3994.1 1884.77  3999.2 1863.89  4004.5 1856.63
  4022.6  1846.6  4097.8 1813.12  4179.9 1811.18  4299.5 1814.63    4493  1816.9
  4620.1 1806.14  4737.2 1806.38  4752.6 1804.25    4785 1806.82  4827.2 1805.97
  4882.4 1808.65  4985.7 1805.22  4995.2 1803.75  4996.6 1801.13  4997.1 1800.63
  5005.7 1801.13  5015.5 1802.49    5031 1807.93  5037.7 1812.49  5044.4 1813.05
  5273.2 1812.53  5324.1 1816.44  5356.4 1824.16  5386.5 1835.23  5451.6 1871.04
#Mann= 7 ,-1 , 0
  3985.3      .1       0  4299.5     .07       0    4493      .1       0
  4996.6     .05       0  5005.7      .1       0  5273.2     .07       0
  5324.1      .1       0
#XS Ineff= 2 , 0
         4458.14 1817.76
Permanent Ineff=
       F       F
Bank Sta=4996.6,5005.7
XS Rating Curve= 0 ,0
Exp/Cntr=0.3,0.1

Type RM Length L Ch R = 1 ,20236   ,535,535,535
BEGIN DESCRIPTION:
Indian Creek 03 41.0
END DESCRIPTION:
XS GIS Cut Line= 4
      1887613.06     13926001.73      1888036.53      13925904.5
      1888416.12     13926112.39      1888775.02     13926575.03
#Sta/Elev= 30
  4152.9 1851.62  4228.6 1817.18  4247.1 1812.54  4311.7    1811  4436.2 1813.58
  4597.2 1814.85  4660.7 1813.68  4698.3 1804.32  4716.3 1803.11  4742.8 1804.31
    4776 1801.46  4846.7 1804.76  4921.2 1803.45    4968 1800.88  4968.5 1800.38
  4977.2 1800.88  4994.7 1801.96  5016.4 1810.62  5312.3 1805.96  5365.2 1803.72
  5423.2 1807.99  5453.1 1817.79  5504.6 1849.48  5540.8 1875.89  5546.4 1882.05
  5553.2 1899.01  5560.1 1907.96  5577.7 1914.67  5592.1 1916.93  5605.7 1915.78
#Mann= 8 ,-1 , 0
  4152.9      .1       0  4436.2     .07       0  4597.2      .1       0
  4921.2     .07       0    4968     .05       0  4977.2     .07       0
  5312.3    .035       0  5365.2      .1       0
Bank Sta=4968,4977.2
XS Rating Curve= 0 ,0
Exp/Cntr=0.3,0.1

Type RM Length L Ch R = 1 ,19701   ,596,596,596
BEGIN DESCRIPTION:
Indian Creek 03 40.0
END DESCRIPTION:
XS GIS Cut Line= 3
        1887675.       13926125.      1888111.17     13926243.51
        1888725.       13926625.
#Sta/Elev= 30
  4585.3 1889.83  4652.1 1877.54  4669.1 1870.79  4675.3 1866.18  4754.8 1849.66
  4806.1 1831.57  4872.1 1820.63  4892.9  1812.7  4913.6 1812.33    4924 1811.43
    4958  1794.2  4958.5  1793.7  4967.2  1794.2  5021.2 1801.06  5044.8 1798.54
  5112.3  1802.5  5140.3 1801.44  5231.9 1802.43  5502.3 1800.71  5541.4    1803
  5576.3 1814.51  5604.6 1829.97  5678.7 1878.04  5680.9 1880.05  5684.5 1888.29
  5685.6 1892.21  5687.4 1903.16  5692.7 1909.85  5726.6 1920.89    5760 1924.79
#Mann= 7 ,-1 , 0
  4585.3      .1       0  4913.6     .07       0    4958     .05       0
  4967.2     .07       0  5140.3      .1       0  5231.9     .07       0
  5502.3      .1       0
Bank Sta=4958,4967.2
XS Rating Curve= 0 ,0
Exp/Cntr=0.3,0.1

Type RM Length L Ch R = 1 ,19105   ,379,379,379
BEGIN DESCRIPTION:
Indian Creek 03 39.0
END DESCRIPTION:
XS GIS Cut Line= 3
        1887625.       13926225.       1888324.6     13926730.93
      1888475.01       13926775.
#Sta/Elev= 30
  4175.8 1863.12  4209.5 1847.88  4268.2 1825.04  4308.3 1812.97  4324.5 1809.17
  4339.5 1808.15  4357.7 1805.04  4407.6 1803.65  4817.5 1801.54  4834.7 1802.58
  4860.5 1800.45  4914.1 1799.32  4946.4 1794.07  4976.5 1795.17    5011 1792.36
  5011.5 1791.86  5020.3 1792.36  5020.8 1793.49    5048 1803.51  5084.7 1826.94
  5093.6 1833.68  5106.4  1840.7  5118.5 1849.68  5130.6 1856.45    5133  1860.7
  5140.5 1879.92  5145.1 1886.32  5147.5 1887.11    5153 1891.72  5195.9 1908.92
#Mann= 5 ,-1 , 0
  4175.8      .1       0  4339.5     .07       0  4914.1      .1       0
    5011     .05       0  5020.3      .1       0
Bank Sta=5011,5020.3
XS Rating Curve= 0 ,0
Exp/Cntr=0.3,0.1

Type RM Length L Ch R = 1 ,18726   ,205,205,205
BEGIN DESCRIPTION:
Indian Creek 03 38.0
END DESCRIPTION:
XS GIS Cut Line= 3
      1887531.19     13926237.97        1887975.       13926875.
      1888375.01     13927025.01
#Sta/Elev= 30
  4216.9 1871.24  4307.3 1818.01  4343.9 1803.09  4392.8 1799.51  4472.6 1799.55
  4595.2 1799.95  4655.2 1800.04  4710.2 1799.48    4825 1796.46  4899.6 1795.78
  4906.9 1793.97  4921.6  1794.7  4932.5  1792.8  4965.4 1794.38  5007.7 1787.42
  5008.2 1786.92    5017 1787.42    5050 1788.26  5073.5 1792.55  5084.9 1797.02
  5108.2 1814.47  5117.6 1817.84  5152.5 1822.54  5193.1 1835.76  5278.5 1874.36
  5313.3 1888.51  5332.7 1898.88    5384 1920.56  5403.2 1927.15  5420.5 1930.51
#Mann= 8 ,-1 , 0
  4216.9      .1       0  4472.6    .035       0  4595.2     .07       0
  4655.2    .035       0  4710.2     .07       0    4825      .1       0
  5007.7     .05       0    5017      .1       0
Bank Sta=5007.7,5017
XS Rating Curve= 0 ,0
Exp/Cntr=0.3,0.1

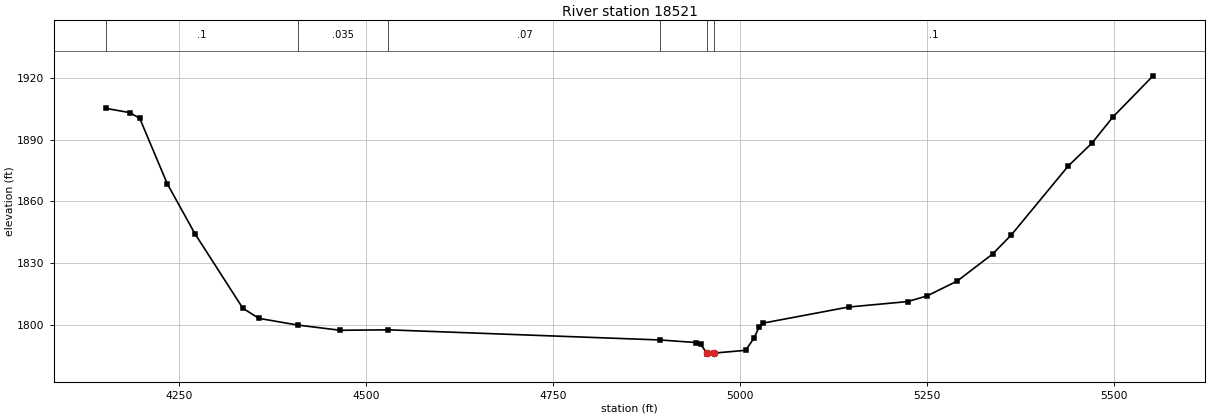
Type RM Length L Ch R = 1 ,18521   ,256,256,256
BEGIN DESCRIPTION:
Mapping XS 9daca95b
END DESCRIPTION:
XS GIS Cut Line= 4
       1887332.8      13926228.4      1887776.83      13926889.5
      1887897.66     13926997.61       1888316.6     13927134.96
#Sta/Elev= 30
  4152.7 1905.14  4184.9 1903.07    4198 1900.25  4234.7 1868.59  4271.7 1844.36
  4335.7 1808.24  4357.2 1803.33  4409.2 1800.07    4466 1797.55  4530.3 1797.77
  4893.5 1792.85  4941.6  1791.6  4947.5  1790.7  4955.9 1786.49  4956.4 1785.99
  4965.2 1786.49  5007.6 1787.83  5019.1 1793.92  5025.6  1799.1    5031 1801.03
  5145.1 1808.82    5224 1811.46  5249.7 1814.16  5290.3  1821.4  5337.7 1834.53
  5362.9 1843.87  5438.7 1877.18  5470.3 1888.24  5498.7 1901.05  5552.1 1920.92
#Mann= 6 ,-1 , 0
  4152.7      .1       0  4409.2    .035       0  4530.3     .07       0
  4893.5      .1       0  4955.9     .05       0  4965.2      .1       0
Bank Sta=4955.9,4965.2
XS Rating Curve= 0 ,0
Exp/Cntr=0.3,0.1