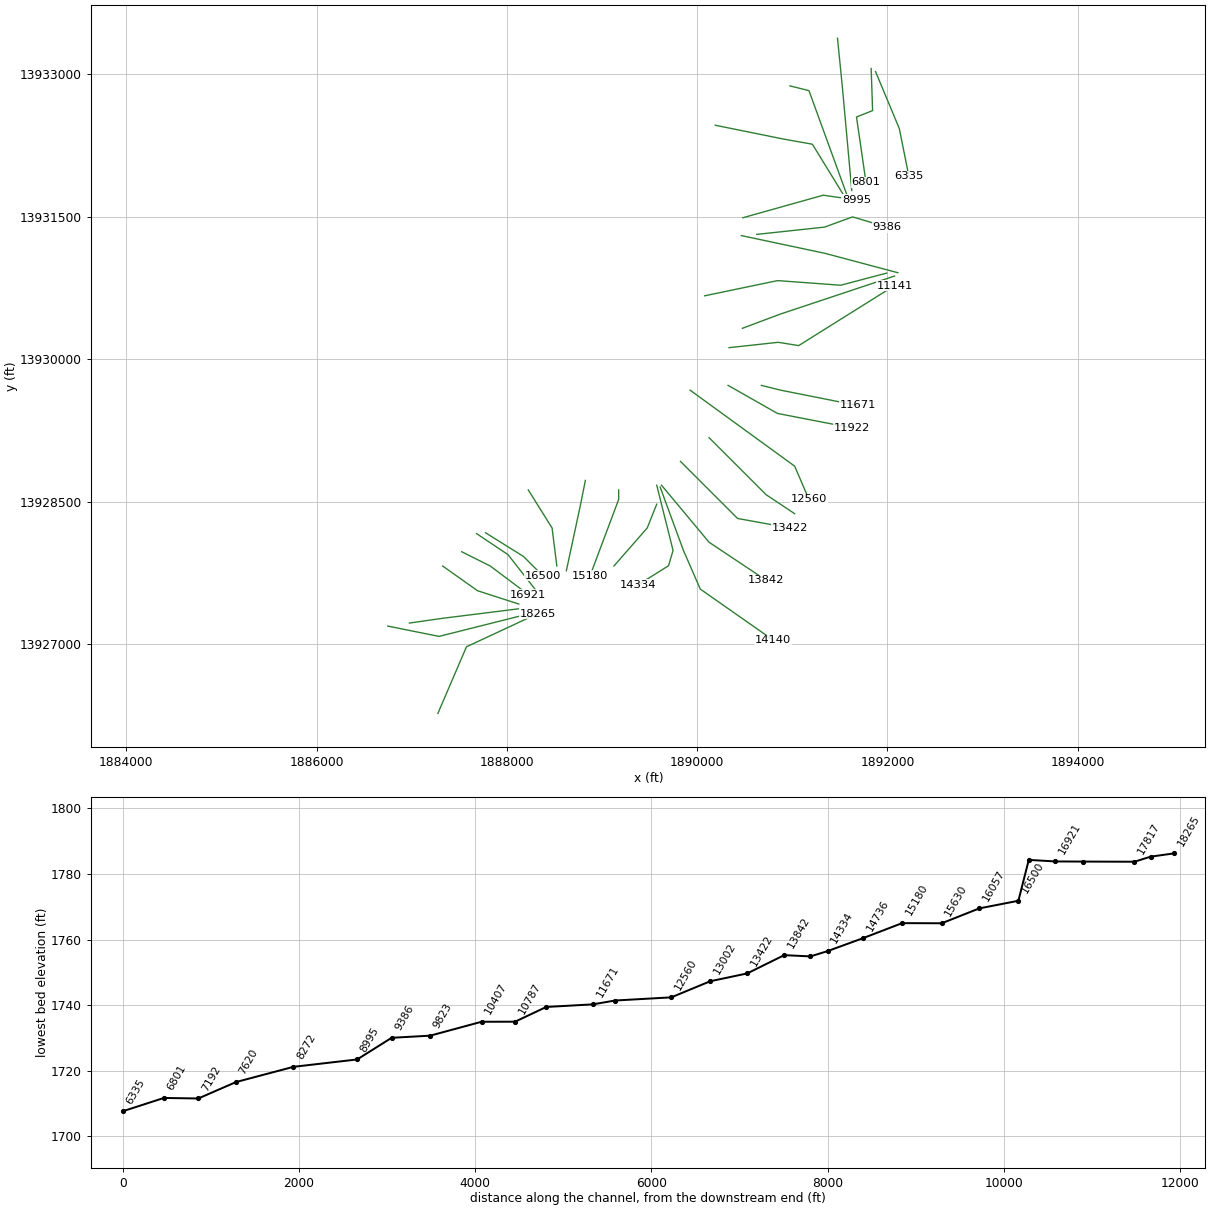
HEC-RAS study Indian Creek 03.prj: Indian Creek 03 Base Level Engineering

--- Indian Creek 03.g01 (geometry) --- (continued)

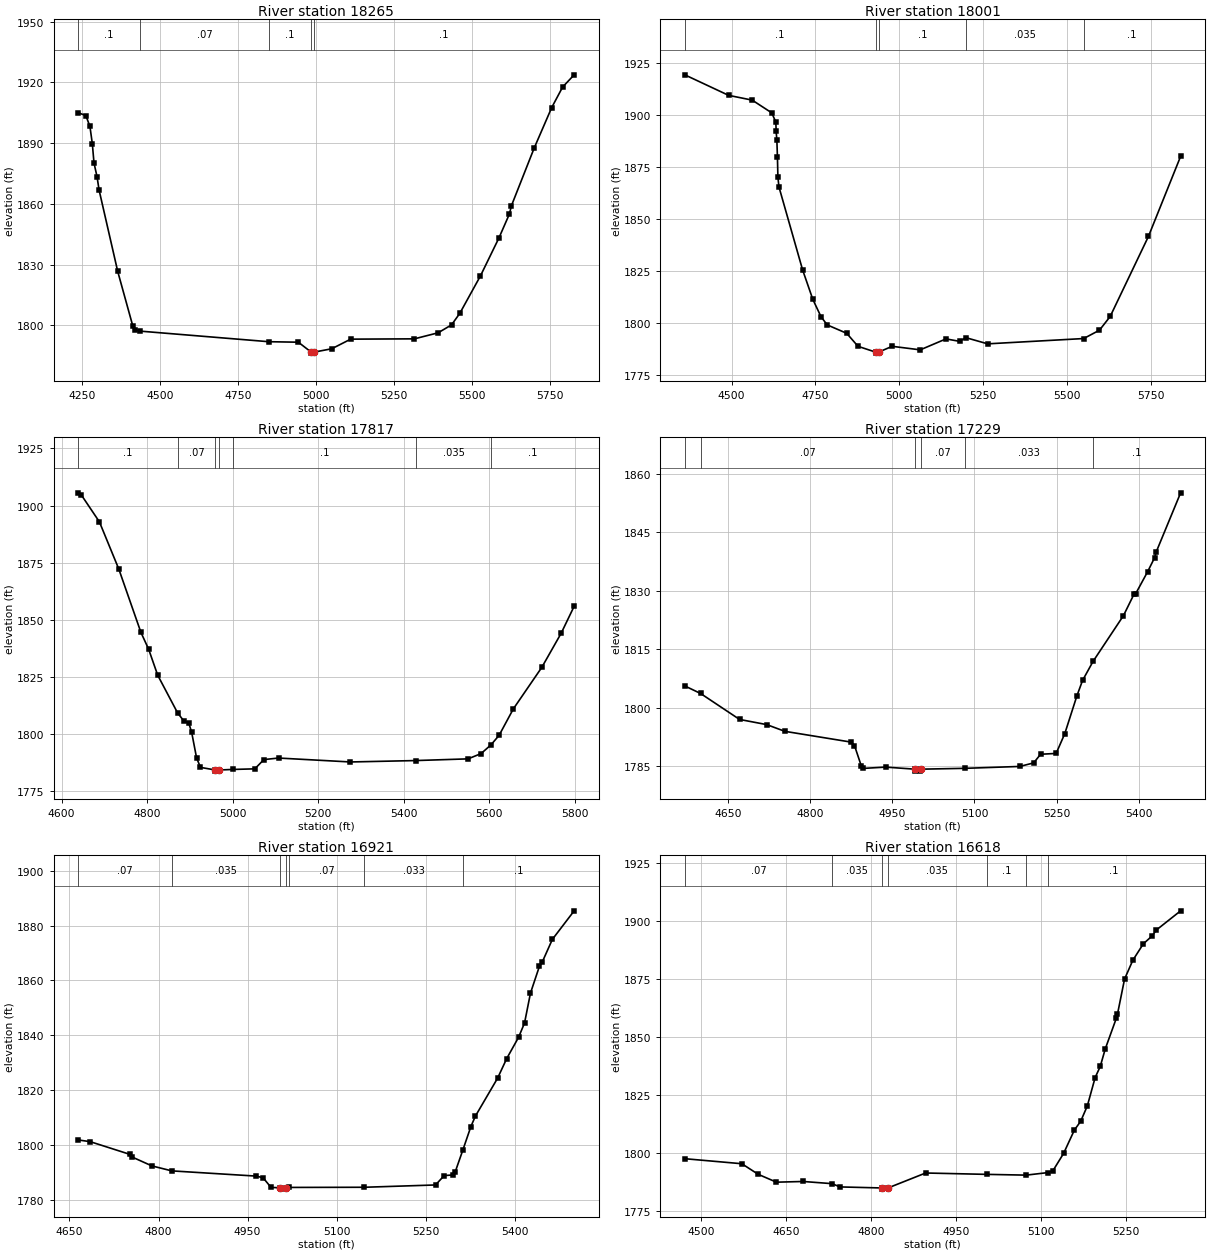
Type RM Length L Ch R = 1 ,18265   ,264,264,264
BEGIN DESCRIPTION:
Indian Creek 03 37.0
END DESCRIPTION:
XS GIS Cut Line= 3
        1887275.     13926275.01        1887575.       13926975.
      1888324.99     13927324.99
#Sta/Elev= 30
  4238.8 1904.94  4262.9 1903.57    4276 1898.19  4283.7 1889.61    4289 1880.18
  4298.8 1873.35  4305.3 1866.82  4365.1  1826.6    4413  1799.9  4419.6 1797.69
  4436.8 1797.16  4849.1 1791.94    4944 1791.69  4985.1  1786.8  4985.6  1786.3
  4994.4  1786.8    5051 1788.45  5111.7  1793.2  5315.8 1793.35  5391.9 1796.33
    5435 1800.25  5461.6 1805.97  5527.7 1824.44  5587.3 1843.29  5620.4 1854.96
    5627 1859.08  5699.8  1887.5  5756.1 1907.54  5791.1 1917.67    5828 1923.68
#Mann= 5 ,-1 , 0
  4238.8      .1       0  4436.8     .07       0  4849.1      .1       0
  4985.1     .05       0  4994.4      .1       0
Bank Sta=4985.1,4994.4
XS Rating Curve= 0 ,0
Exp/Cntr=0.3,0.1

Type RM Length L Ch R = 1 ,18001   ,184,184,184
BEGIN DESCRIPTION:
Mapping XS 78713eac
END DESCRIPTION:
XS GIS Cut Line= 3
      1886748.89     13927192.98       1887286.9     13927084.71
      1888187.37     13927311.16
#Sta/Elev= 30
  4360.8 1919.27  4491.4 1909.39  4561.7 1907.09  4619.8 1900.97  4632.1 1896.52
    4633 1892.03  4635.1 1887.74  4636.8  1879.8  4638.2 1869.98  4641.3 1865.34
  4711.6 1825.47  4742.2  1811.2  4766.7 1802.82  4785.1  1798.9  4843.2 1794.85
  4876.9 1788.59  4929.1 1785.81  4929.6 1785.31  4938.5 1785.81  4978.6 1788.59
  5062.3 1786.89    5139 1792.16  5179.7 1790.98  5198.1 1792.76  5263.2 1789.78
  5549.3 1792.33  5596.3 1796.35  5628.2 1802.95  5742.1 1841.45  5838.1 1880.04
#Mann= 5 ,-1 , 0
  4360.8      .1       0  4929.1     .05       0  4938.5      .1       0
  5198.1    .035       0  5549.3      .1       0
Bank Sta=4929.1,4938.5
XS Rating Curve= 0 ,0
Exp/Cntr=0.3,0.1

Type RM Length L Ch R = 1 ,17817   ,588,588,588
BEGIN DESCRIPTION:
Indian Creek 03 36.0
END DESCRIPTION:
XS GIS Cut Line= 3
      1886975.04     13927225.01        1887325.       13927275.
      1888124.96     13927374.99
#Sta/Elev= 30
    4639 1905.57  4645.9 1904.67  4688.3 1892.86  4733.8 1872.13  4785.3 1844.52
  4803.5 1837.09  4824.6 1825.76  4871.1 1809.27  4885.6 1805.76  4897.4 1804.75
  4904.1 1800.73  4915.6 1789.52  4924.7  1785.4  4959.3 1784.26  4959.8 1783.76
  4968.8 1784.26  5001.4  1784.5  5051.8 1784.76    5073 1788.81  5107.2 1789.49
  5275.5 1787.77  5429.1 1788.39  5550.6 1789.13  5580.9 1791.43  5604.1 1795.24
  5623.2 1799.45  5656.5 1811.02    5723 1829.17  5768.3 1844.11  5798.7 1855.92
#Mann= 7 ,-1 , 0
    4639      .1       0  4871.1     .07       0  4959.3     .05       0
  4968.8     .07       0  5001.4      .1       0  5429.1    .035       0
  5604.1      .1       0
Bank Sta=4959.3,4968.8
XS Rating Curve= 0 ,0
Exp/Cntr=0.3,0.1

Type RM Length L Ch R = 1 ,17229   ,308,308,308
BEGIN DESCRIPTION:
Indian Creek 03 35.0
END DESCRIPTION:
XS GIS Cut Line= 3
      1887324.96     13927825.03      1887691.02     13927565.23
      1888125.05     13927424.99
#Sta/Elev= 30
  4571.3 1805.62  4600.1 1803.69  4671.3 1797.04  4720.8 1795.72  4753.9    1794
  4875.3 1791.23    4881 1790.37  4893.7 1785.04  4897.3 1784.51  4937.8 1784.84
  4991.5 1784.31    4992 1783.81  5001.3 1783.81  5001.8 1784.31  5083.5 1784.53
  5182.8 1785.01  5208.1 1785.92  5220.7 1788.13  5249.1 1788.34  5264.9 1793.42
  5286.9 1803.05  5297.3 1807.03  5316.5 1811.91    5372 1823.63    5391 1829.05
  5394.1 1829.19  5416.2  1834.9  5428.8 1838.46  5431.9 1839.98  5476.3 1855.06
#Mann= 6 ,-1 , 0
  4571.3    .035       0  4600.1     .07       0  4991.5     .05       0
  5001.8     .07       0  5083.5    .033       0  5316.5      .1       0
Bank Sta=4991.5,5001.8
XS Rating Curve= 0 ,0
Exp/Cntr=0.3,0.1

Type RM Length L Ch R = 1 ,16921   ,303,303,303
BEGIN DESCRIPTION:
Indian Creek 03 34.0
END DESCRIPTION:
XS GIS Cut Line= 3
      1887525.02     13927974.99        1887825.       13927825.
      1888225.01       13927525.
#Sta/Elev= 30
  4664.9 1801.79  4684.8 1801.18  4751.9 1796.53  4755.3 1795.59  4788.8 1792.33
  4822.4 1790.51    4965  1788.6  4976.2 1787.99  4989.6 1784.47  5005.1 1784.35
  5005.6 1783.85  5015.4 1784.35  5020.6 1784.47  5146.9 1784.53  5266.7 1785.37
  5281.3 1788.79  5296.7 1789.04  5300.1 1790.27  5312.6 1798.02  5326.3 1806.68
  5333.8 1810.46  5371.3 1824.35  5386.7 1831.52  5406.7 1839.29  5416.7 1844.49
  5426.7  1855.4  5441.7 1865.14  5446.7 1866.82  5463.6 1875.02  5500.3 1885.43
#Mann= 7 ,-1 , 0
  4664.9     .07       0  4822.4    .035       0  5005.1    .035       0
  5015.4    .035       0  5020.6     .07       0  5146.9    .033       0
  5312.6      .1       0
Bank Sta=5005.1,5015.4
XS Rating Curve= 0 ,0
Exp/Cntr=0.3,0.1

Type RM Length L Ch R = 1 ,16618   ,118,118,118
BEGIN DESCRIPTION:
Mapping XS 45a76a0f
END DESCRIPTION:
XS GIS Cut Line= 3
      1887681.18     13928165.94      1888012.57     13927943.95
      1888305.75     13927568.29
#Sta/Elev= 30
  4471.6 1797.45  4572.3 1795.28  4601.2 1790.71  4633.4 1787.32  4680.6 1787.62
  4731.6 1786.68  4745.6 1785.27  4819.9 1784.82  4820.4 1784.32  4830.3 1784.82
  4896.8 1791.28  5004.7 1790.69  5074.3 1790.36  5112.4 1791.45  5121.4  1792.2
  5140.4 1799.74  5159.4 1809.81  5170.5 1813.58  5182.3 1820.25  5196.1 1832.49
  5205.1 1837.27  5213.9 1844.81  5233.4 1858.02  5235.5 1859.83    5248 1874.97
  5262.6  1883.1  5281.2 1890.21  5296.8 1893.63    5304 1896.13    5347 1904.44
#Mann= 7 ,-1 , 0
  4471.6     .07       0  4731.6    .035       0  4819.9    .035       0
  4830.3    .035       0  5004.7      .1       0  5074.3    .035       0
  5112.4      .1       0
Bank Sta=4819.9,4830.3
XS Rating Curve= 0 ,0
Exp/Cntr=0.3,0.1

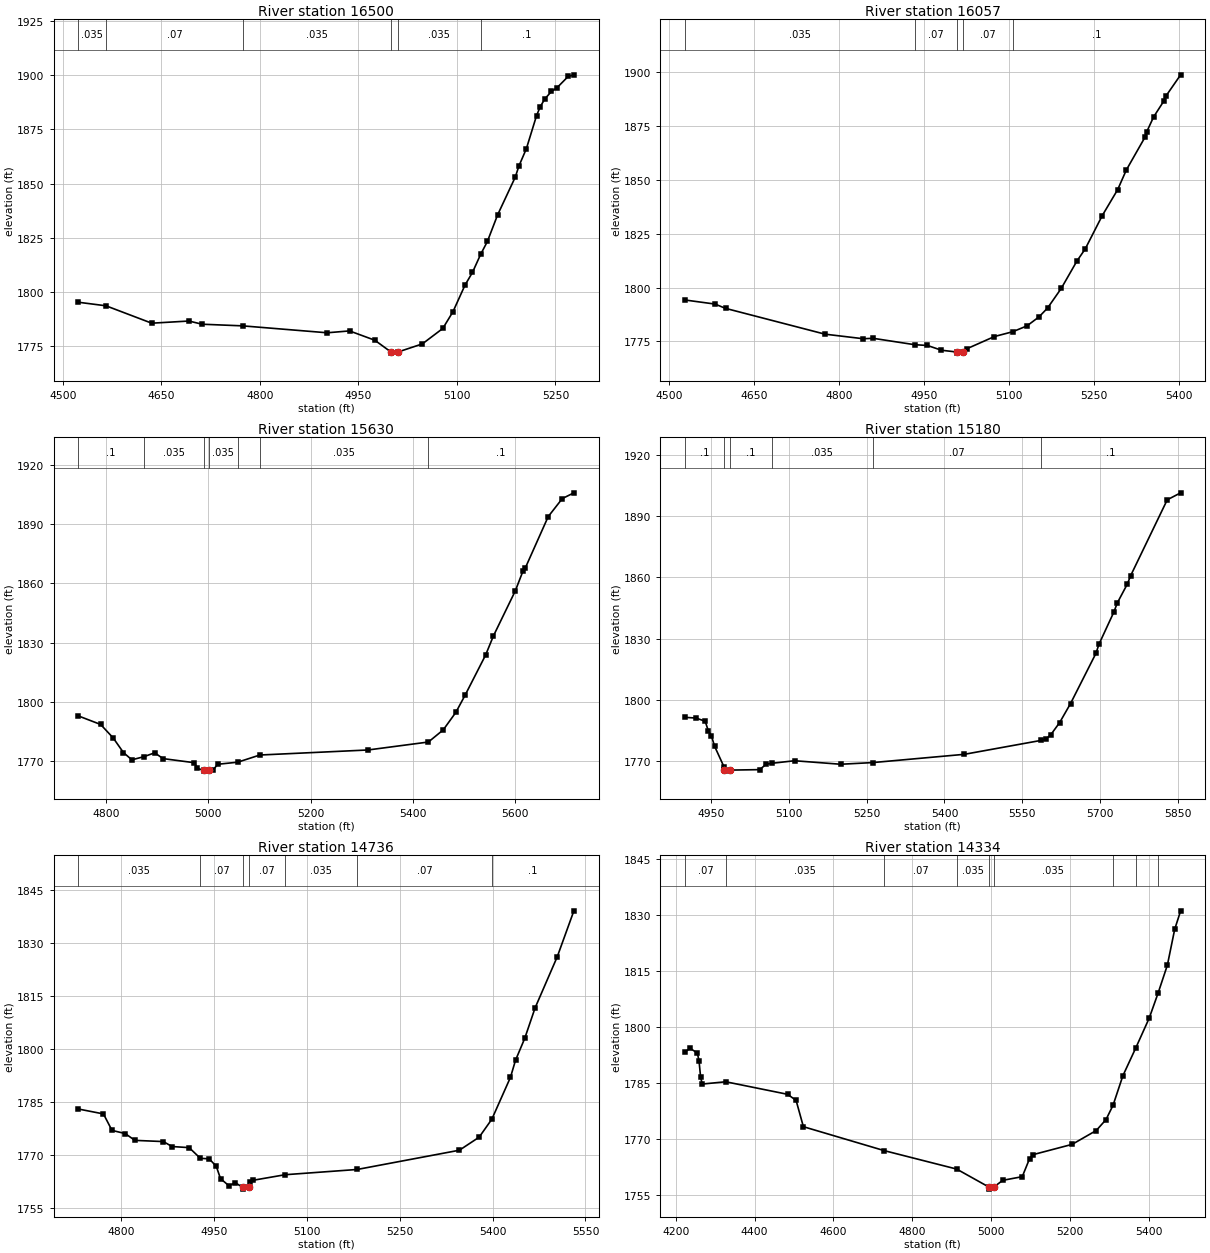
Type RM Length L Ch R = 1 ,16500   ,443,443,443
BEGIN DESCRIPTION:
Indian Creek 03 33.0
END DESCRIPTION:
XS GIS Cut Line= 3
      1887775.03     13928174.98        1888175.       13927925.
      1888374.99     13927725.01
#Sta/Elev= 30
  4523.5 1795.32  4565.6 1793.68  4635.3 1785.66  4691.9 1786.66  4711.9 1785.19
  4773.7 1784.43  4902.4 1781.24  4936.4  1782.1  4974.9 1777.81  4999.6 1772.36
  5000.1 1771.86    5010 1772.36  5047.3 1776.12  5078.4 1783.23  5093.9 1790.95
  5112.3 1803.25  5123.6 1809.08    5136 1817.37  5146.3 1823.33  5161.8 1835.54
  5188.7 1852.96  5194.3 1858.11  5205.7 1866.14  5221.2 1881.39  5226.9 1885.54
  5233.9  1889.1  5243.8 1892.49  5252.3  1894.2  5269.3 1899.42    5278 1900.16
#Mann= 6 ,-1 , 0
  4523.5    .035       0  4565.6     .07       0  4773.7    .035       0
  4999.6    .035       0    5010    .035       0    5136      .1       0
Bank Sta=4999.6,5010
XS Rating Curve= 0 ,0
Exp/Cntr=0.3,0.1

Type RM Length L Ch R = 1 ,16057   ,427,427,427
BEGIN DESCRIPTION:
Indian Creek 03 32.0
END DESCRIPTION:
XS GIS Cut Line= 3
      1888224.98     13928625.03        1888475.       13928225.
      1888525.01     13927824.95
#Sta/Elev= 30
  4528.3 1794.21  4581.2 1792.32  4599.7 1790.33  4775.2 1778.35    4843 1776.22
  4860.1 1776.43  4933.5 1773.46  4956.2 1773.09    4981 1770.88  5008.7 1770.04
  5009.2 1769.54  5019.2 1770.04  5026.1 1771.61  5074.5 1777.25  5106.7 1779.47
  5131.9 1782.19  5153.1 1786.36  5168.2 1790.46  5192.4 1799.59  5220.1 1812.31
  5234.7 1817.91  5264.9 1833.45  5292.1  1845.5  5307.3 1854.58  5340.5 1869.92
  5343.5 1872.43  5355.6 1879.28  5373.8 1886.72  5376.8 1888.76  5403.2 1898.78
#Mann= 5 ,-1 , 0
  4528.3    .035       0  4933.5     .07       0  5008.7     .05       0
  5019.2     .07       0  5106.7      .1       0
Bank Sta=5008.7,5019.2
XS Rating Curve= 0 ,0
Exp/Cntr=0.3,0.1

Type RM Length L Ch R = 1 ,15630   ,450,450,450
BEGIN DESCRIPTION:
Indian Creek 03 31.0
END DESCRIPTION:
XS GIS Cut Line= 3
      1888825.01     13928725.03        1888775.       13928475.
        1888625.     13927774.98
#Sta/Elev= 30
  4745.1 1792.94  4788.8 1788.61  4813.3 1781.83  4833.5  1774.4    4850 1770.72
  4873.6 1772.31  4894.7 1774.27  4911.2 1771.33  4972.4 1769.26  4978.5 1766.33
  4990.5  1765.5    4991    1765  5001.2  1765.5  5009.1 1765.62  5018.3 1768.47
  5057.5 1769.53  5100.7 1773.15  5312.6  1775.7    5431 1779.73  5460.1 1785.89
  5484.7 1794.71  5503.1 1803.53    5543  1823.7  5558.3 1833.37  5601.3 1856.24
  5616.6 1866.46  5620.8 1867.77  5665.7 1893.78  5693.3  1902.9    5716 1905.81
#Mann= 7 ,-1 , 0
  4745.1      .1       0  4873.6    .035       0  4990.5    .035       0
  5001.2    .035       0  5057.5     .07       0  5100.7    .035       0
    5431      .1       0
Bank Sta=4990.5,5001.2
XS Rating Curve= 0 ,0
Exp/Cntr=0.3,0.1

Type RM Length L Ch R = 1 ,15180   ,444,444,444
BEGIN DESCRIPTION:
Indian Creek 03 30.0
END DESCRIPTION:
XS GIS Cut Line= 3
        1889175.     13928624.98        1889175.       13928525.
      1888874.99     13927724.98
#Sta/Elev= 30
  4900.4 1791.39  4921.4 1791.04  4939.1 1789.48  4945.2 1784.79  4951.2 1782.27
  4957.2 1777.24  4975.4 1767.12    4976 1765.54  4976.5 1765.04  4986.7 1765.54
    5044 1765.77  5056.8 1768.45  5067.6 1768.88  5111.3 1770.13    5200 1768.41
  5261.9 1769.23  5438.1 1773.27    5585 1780.05  5595.1 1780.66  5604.7 1782.86
  5621.8 1788.84  5642.7 1798.12  5691.7 1822.76  5697.6 1827.26  5726.1 1842.92
  5732.9 1847.48  5752.1 1856.67  5758.5 1860.78    5829 1897.96  5854.8 1901.38
#Mann= 6 ,-1 , 0
  4900.4      .1       0    4976     .05       0  4986.7      .1       0
  5067.6    .035       0  5261.9     .07       0    5585      .1       0
Bank Sta=4976,4986.7
XS Rating Curve= 0 ,0
Exp/Cntr=0.3,0.1

Type RM Length L Ch R = 1 ,14736   ,402,402,402
BEGIN DESCRIPTION:
Indian Creek 03 29.0
END DESCRIPTION:
XS GIS Cut Line= 3
      1889575.01     13928475.03        1889475.       13928225.
        1889125.       13927825.
#Sta/Elev= 30
  4730.5 1783.08  4771.1 1781.69  4784.9 1777.04  4806.3 1776.14  4821.9 1774.22
    4868 1773.88  4881.9 1772.48  4909.6 1772.17  4927.7 1769.15    4942 1769.01
  4953.4  1766.9  4960.3 1763.41  4973.9  1761.4    4984 1762.26  4996.3 1760.95
  4996.8 1760.45  5007.1 1760.95  5008.1 1762.45  5012.3 1762.93  5064.7 1764.52
    5181    1766  5346.3 1771.44  5378.2 1775.12  5398.7 1780.19  5428.8 1792.02
    5437 1796.85  5451.9 1803.04  5468.6 1811.63  5504.5 1826.11  5531.3 1839.05
#Mann= 7 ,-1 , 0
  4730.5    .035       0  4927.7     .07       0  4996.3     .05       0
  5007.1     .07       0  5064.7    .035       0    5181     .07       0
  5398.7      .1       0
Bank Sta=4996.3,5007.1
XS Rating Curve= 0 ,0
Exp/Cntr=0.3,0.1

Type RM Length L Ch R = 1 ,14334   ,194,194,194
BEGIN DESCRIPTION:
Indian Creek 03 28.0
END DESCRIPTION:
XS GIS Cut Line= 4
      1889575.01     13928674.97      1889746.66     13927988.38
      1889698.68      13927827.3        1889375.       13927625.
#Sta/Elev= 30
  4223.7 1793.32  4236.4 1794.31  4254.9    1793  4259.2 1790.82  4263.2 1786.47
  4267.3  1784.7    4327 1785.31  4483.7 1781.95  4505.4 1780.32  4523.9 1773.26
  4729.3 1766.83  4912.9 1761.89  4995.6 1757.01  4996.1 1756.51  5006.5 1757.01
  5029.7 1758.87  5079.3 1759.85    5098 1764.72  5107.8 1765.79  5205.9 1768.52
    5267 1772.23  5291.8 1775.16  5309.8 1779.04  5334.6 1786.92  5367.2 1794.35
  5401.5  1802.4  5423.8 1809.04  5447.5 1816.58  5466.1  1826.2  5481.2 1831.17
#Mann= 9 ,-1 , 0
  4223.7     .07       0    4327    .035       0  4729.3     .07       0
  4912.9    .035       0  4995.6    .035       0  5006.5    .035       0
  5309.8      .1       0  5367.2    .035       0  5423.8      .1       0
Bank Sta=4995.6,5006.5
XS Rating Curve= 0 ,0
Exp/Cntr=0.3,0.1

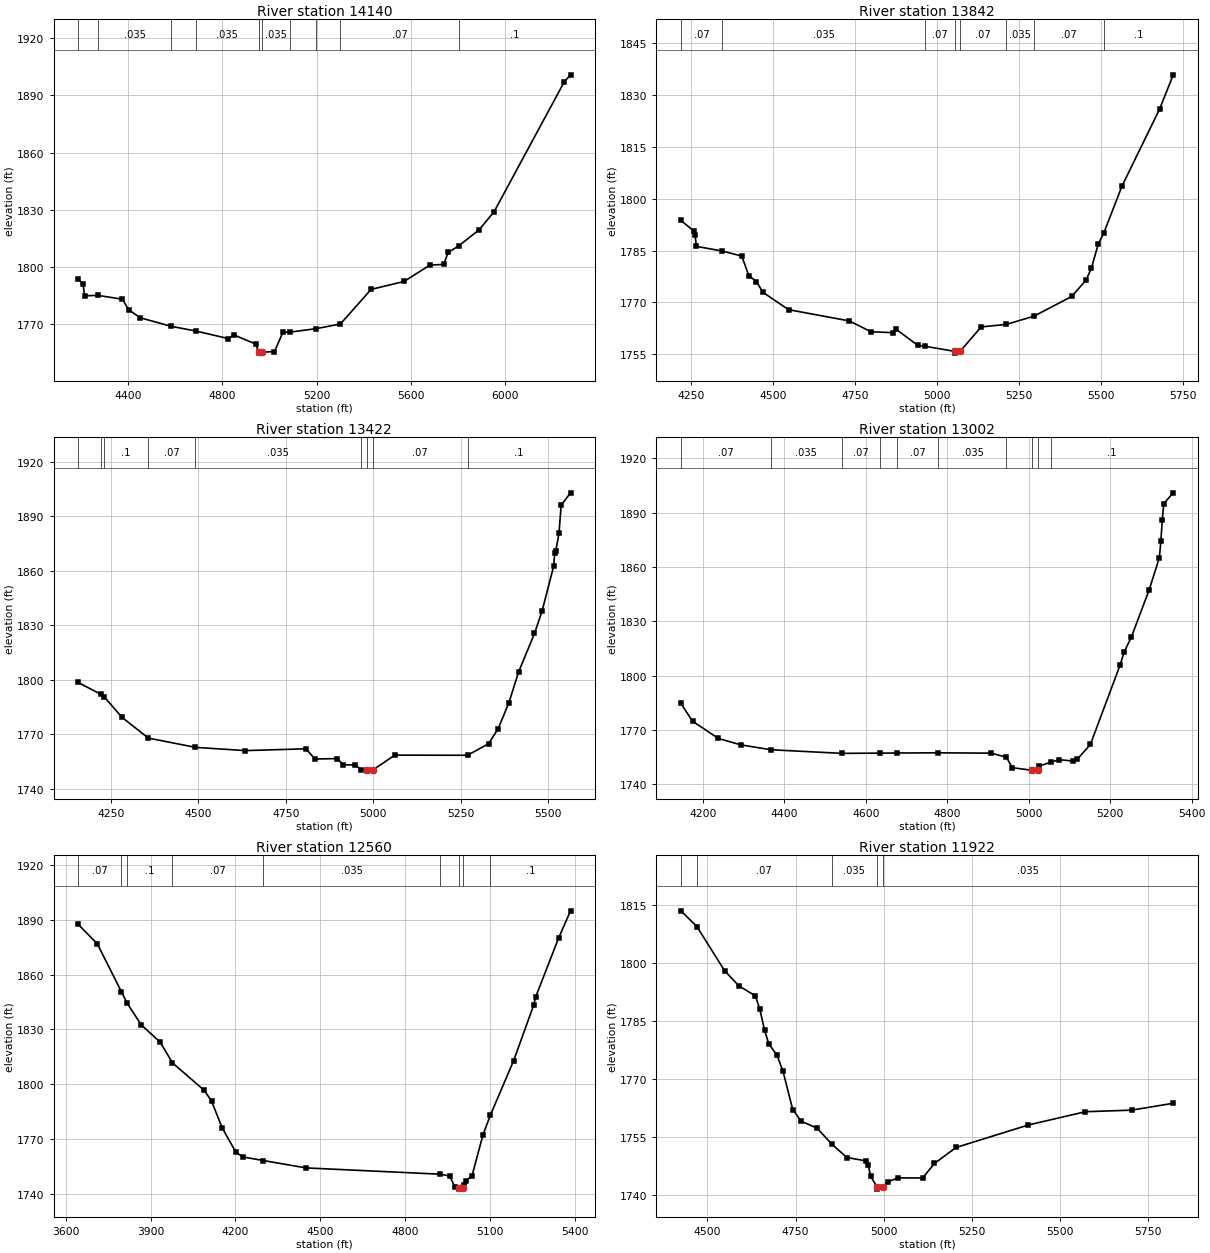
Type RM Length L Ch R = 1 ,14140   ,298,298,298
BEGIN DESCRIPTION:
Mapping XS 3800a525
END DESCRIPTION:
XS GIS Cut Line= 4
      1889610.89     13928655.13      1889855.67      13927988.5
      1890032.75     13927582.25      1890798.39     13927045.78
#Sta/Elev= 30
  4188.7 1793.56  4209.4 1791.28  4215.8 1784.93    4273 1785.15  4376.6 1783.15
  4402.3 1777.67  4452.3 1773.42  4583.7 1768.93  4687.2  1766.5  4825.4 1762.52
  4848.6 1764.48  4942.3 1759.61  4954.3  1755.4  4954.8  1754.9  4969.5  1755.4
  5021.3 1755.72  5056.8 1765.77  5088.5 1765.94  5195.3 1767.67  5300.8 1770.15
    5431  1788.3  5570.6 1792.44  5680.1 1800.99  5738.6 1801.41    5758 1807.66
  5802.3 1811.08  5888.9 1819.49  5952.9 1829.06  6250.9 1897.21  6276.9 1900.73
#Mann= 10 ,-1 , 0
  4188.7     .07       0    4273    .035       0  4583.7     .07       0
  4687.2    .035       0  4954.3    .035       0  4969.5    .035       0
  5088.5     .07       0  5195.3    .035       0  5300.8     .07       0
  5802.3      .1       0
Bank Sta=4954.3,4969.5
XS Rating Curve= 0 ,0
Exp/Cntr=0.3,0.1

Type RM Length L Ch R = 1 ,13842   ,420,420,420
BEGIN DESCRIPTION:
Indian Creek 03 27.0
END DESCRIPTION:
XS GIS Cut Line= 3
      1889625.03     13928674.97        1890125.       13928075.
      1890725.01       13927675.
#Sta/Elev= 30
  4218.8 1793.73  4258.2 1790.68  4262.1 1789.49  4266.3 1786.21  4344.9 1784.86
  4404.7 1783.39  4426.1 1777.74  4449.3 1776.02  4469.1 1772.91  4547.2 1767.87
  4732.8 1764.61  4798.8 1761.48  4864.8 1761.21  4875.8 1762.18  4941.4 1757.54
    4965 1757.24  5055.4 1755.78  5055.9 1755.28  5070.6 1755.78  5135.1 1762.88
  5211.6  1763.6  5295.6 1765.97  5411.4 1771.71  5454.6  1776.4  5470.9  1779.8
  5492.5 1786.99  5508.9 1790.06  5564.2  1803.6  5679.6 1826.06  5720.9 1835.91
#Mann= 8 ,-1 , 0
  4218.8     .07       0  4344.9    .035       0    4965     .07       0
  5055.4     .05       0  5070.6     .07       0  5211.6    .035       0
  5295.6     .07       0  5508.9      .1       0
Bank Sta=5055.4,5070.6
XS Rating Curve= 0 ,0
Exp/Cntr=0.3,0.1

Type RM Length L Ch R = 1 ,13422   ,420,420,420
BEGIN DESCRIPTION:
Indian Creek 03 26.0
END DESCRIPTION:
XS GIS Cut Line= 3
      1889824.99     13928925.01        1890425.       13928325.
      1890975.04     13928224.99
#Sta/Elev= 30
  4156.3 1798.52  4222.1 1791.89  4230.5 1790.68  4281.6 1779.33  4356.9  1767.9
  4491.7 1762.79  4633.8 1761.01  4807.3 1761.99  4833.2 1756.38  4896.8 1756.62
  4913.8 1753.24  4947.7 1753.06  4965.7 1750.59  4982.6 1750.21  4983.1 1749.71
  4997.8 1750.21  5061.4 1758.51  5269.4 1758.44  5329.7  1764.8  5357.1 1773.17
  5387.6 1787.31  5415.1 1804.17  5460.8 1825.47  5482.1 1837.58  5515.7 1862.57
  5518.7 1870.03  5521.8 1871.03  5530.9 1880.77    5537 1896.04  5563.9  1902.9
#Mann= 9 ,-1 , 0
  4156.3     .07       0  4222.1    .035       0  4230.5      .1       0
  4356.9     .07       0  4491.7    .035       0  4965.7     .07       0
  4982.6     .05       0  4997.8     .07       0  5269.4      .1       0
Bank Sta=4982.6,4997.8
XS Rating Curve= 0 ,0
Exp/Cntr=0.3,0.1

Type RM Length L Ch R = 1 ,13002   ,442,442,442
BEGIN DESCRIPTION:
Indian Creek 03 25.0
END DESCRIPTION:
XS GIS Cut Line= 3
      1890125.03     13929174.97        1890725.       13928575.
      1891024.97     13928375.02
#Sta/Elev= 30
  4145.8 1784.72  4174.5 1774.85  4238.1 1765.34  4293.3 1761.79    4367 1759.12
    4541 1757.12  4634.2 1757.25  4675.8 1757.32  4778.2 1757.42  4907.5 1757.24
  4945.3    1755  4959.4 1749.23  5006.8 1747.82  5007.3 1747.32  5022.1 1747.82
  5025.5 1750.06  5054.8 1752.31  5075.5 1753.62    5108 1752.89  5118.8 1753.76
  5151.3 1762.02  5224.3 1805.84  5234.2 1812.99  5252.2 1821.45  5295.5 1847.24
  5320.7 1865.07  5324.3 1874.06  5327.9 1885.93  5331.5 1894.91  5354.8 1900.87
#Mann= 10 ,-1 , 0
  4145.8     .07       0    4367    .035       0    4541     .07       0
  4634.2    .035       0  4675.8     .07       0  4778.2    .035       0
  4945.3     .07       0  5006.8     .05       0  5022.1     .07       0
  5054.8      .1       0
Bank Sta=5006.8,5022.1
XS Rating Curve= 0 ,0
Exp/Cntr=0.3,0.1

Type RM Length L Ch R = 1 ,12560   ,638,638,638
BEGIN DESCRIPTION:
Indian Creek 03 24.0
END DESCRIPTION:
XS GIS Cut Line= 3
      1889925.02     13929674.99        1891025.       13928875.
      1891174.99     13928525.01
#Sta/Elev= 30
  3644.1 1887.66  3711.6 1877.04  3797.3 1850.63  3817.3 1844.43  3867.4 1832.48
  3934.2 1823.05  3977.4 1811.69    4090 1796.58  4115.9 1790.67    4153 1776.09
  4202.3 1762.52  4227.5 1760.04  4298.2 1758.11  4449.8 1754.05  4924.2  1750.6
    4958 1749.58  4976.5 1743.31  4990.8 1742.91  4991.3 1742.41  5006.1 1742.91
  5006.7 1744.72  5014.1 1747.13  5036.1 1749.43  5075.3 1772.15  5101.4 1782.95
  5183.5 1812.79  5254.8 1843.44  5261.3 1847.71  5342.9  1880.2    5385 1895.09
#Mann= 9 ,-1 , 0
  3644.1     .07       0  3797.3    .035       0  3817.3      .1       0
  3977.4     .07       0  4298.2    .035       0  4924.2     .07       0
  4990.8     .05       0  5006.1     .07       0  5101.4      .1       0
Bank Sta=4990.8,5006.1
XS Rating Curve= 0 ,0
Exp/Cntr=0.3,0.1

Type RM Length L Ch R = 1 ,11922   ,251,251,251
BEGIN DESCRIPTION:
Indian Creek 03 23.0
END DESCRIPTION:
XS GIS Cut Line= 3
      1890324.97     13929725.02      1890843.68     13929429.78
      1891628.12     13929277.65
#Sta/Elev= 30
  4424.7  1813.5  4470.3 1809.42  4548.6 1798.01  4589.7 1794.03  4635.9  1791.5
  4648.7 1787.96  4661.9 1782.63    4674 1779.06    4697 1776.16  4714.2 1771.99
  4741.9 1762.04    4766 1759.01  4810.9 1757.25  4851.8 1753.16  4895.4 1749.63
    4949 1748.78  4955.9 1747.66  4962.8 1744.75  4981.4 1741.95  4981.9 1741.45
  4997.4 1741.95  5011.1 1743.36  5041.2 1744.37  5110.1 1744.33  5143.7  1748.1
  5204.8 1752.23  5409.6 1758.05  5571.5 1761.49  5702.9  1761.9  5820.6 1763.68
#Mann= 5 ,-1 , 0
  4424.7      .1       0  4470.3     .07       0  4851.8    .035       0
  4981.4    .035       0  4997.4    .035       0
Bank Sta=4981.4,4997.4
XS Rating Curve= 0 ,0
Exp/Cntr=0.3,0.1

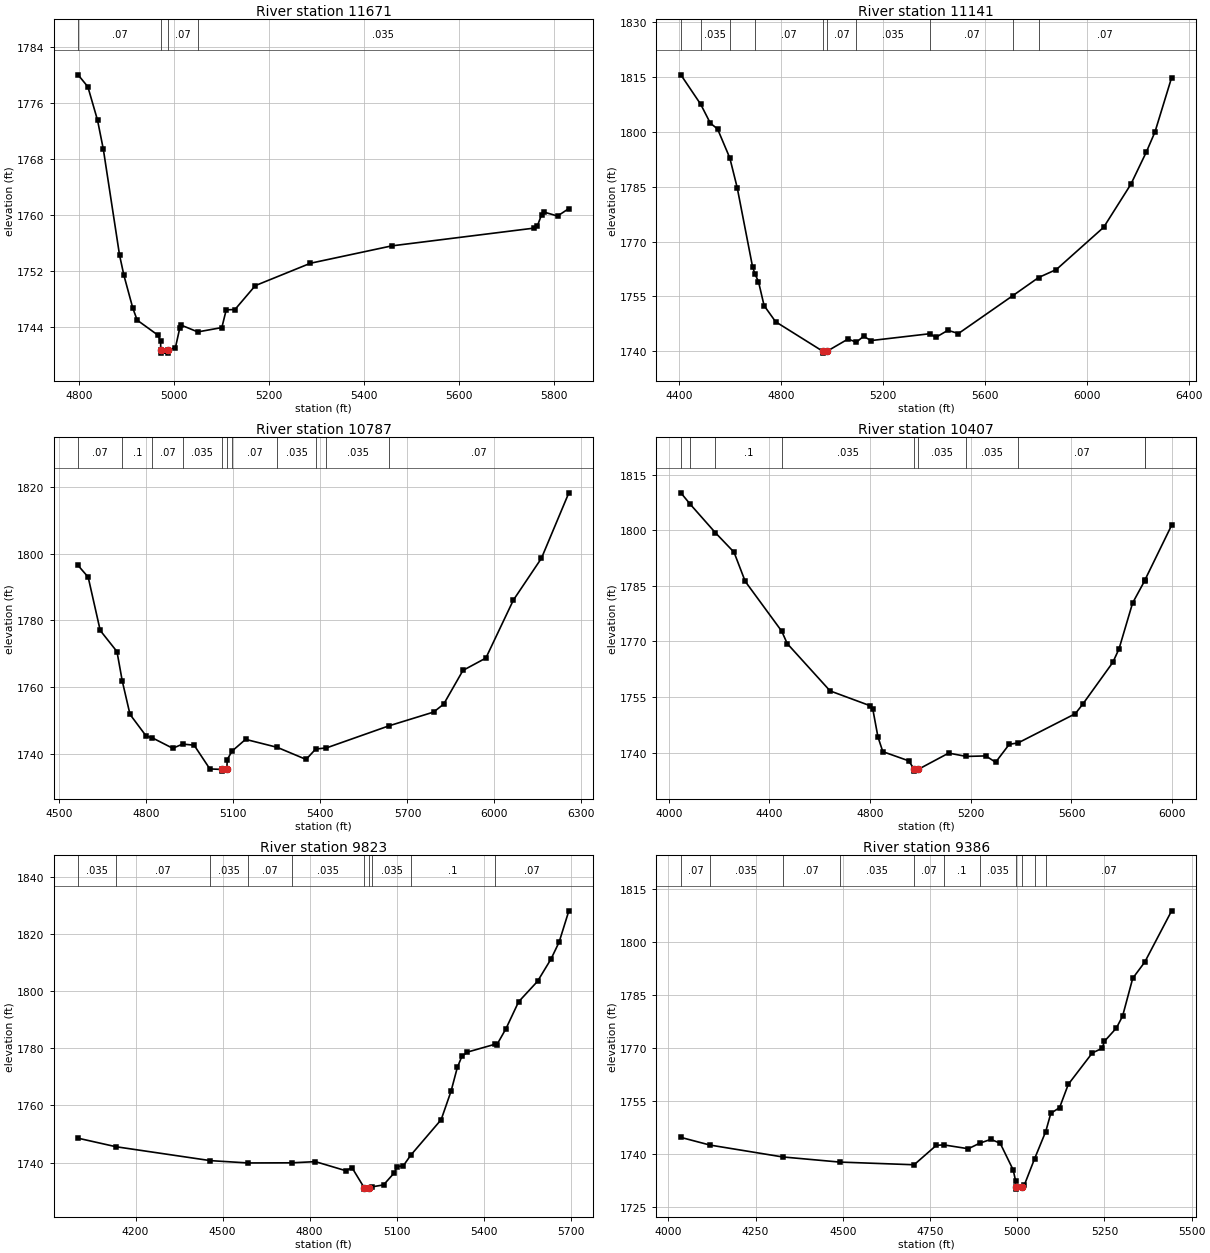
Type RM Length L Ch R = 1 ,11671   ,530,530,530
BEGIN DESCRIPTION:
Indian Creek 03 22.0
END DESCRIPTION:
XS GIS Cut Line= 3
      1890674.97     13929725.01        1890875.       13929675.
      1891685.94     13929513.75
#Sta/Elev= 30
    4798 1780.03  4818.6 1778.32  4838.9 1773.56  4851.2 1769.38  4885.2 1754.31
  4894.5 1751.38  4913.1 1746.73  4922.4 1744.99  4965.6 1742.87  4971.8 1742.01
  4971.9 1740.78  4972.4 1740.28  4987.4 1740.28  4987.9 1740.78  5002.8 1741.04
  5011.9 1743.82    5015 1744.28  5049.9 1743.31  5100.6 1743.93  5109.8 1746.46
  5128.2 1746.51    5171 1749.92  5287.2 1753.12  5458.3  1755.6  5758.3 1758.14
  5764.4  1758.4  5773.6 1760.04  5779.6 1760.41  5807.2 1759.86    5831 1760.93
#Mann= 4 ,-1 , 0
    4798     .07       0  4971.9     .05       0  4987.9     .07       0
  5049.9    .035       0
Bank Sta=4971.9,4987.9
XS Rating Curve= 0 ,0
Exp/Cntr=0.3,0.1

Type RM Length L Ch R = 1 ,11141   ,354,354,354
BEGIN DESCRIPTION:
Indian Creek 03 21.0
END DESCRIPTION:
XS GIS Cut Line= 4
      1890335.71     13930121.54       1890852.2     13930177.96
      1891067.05     13930143.24      1892075.02     13930775.02
#Sta/Elev= 30
    4406  1815.6  4483.9 1807.55  4521.6 1802.39  4550.2 1800.78  4598.2 1792.86
  4627.2 1784.75  4687.6 1763.06    4697 1761.13  4710.8 1759.03  4732.8 1752.48
  4778.1 1748.06  4963.5 1739.98    4964 1739.48  4979.6 1739.98  5062.7 1743.35
  5094.9 1742.45  5123.5  1744.1  5152.1 1742.91  5383.9 1744.79  5406.6 1743.78
  5454.4 1745.72  5495.8 1744.84  5710.1 1755.24  5810.6 1760.16  5880.3 1762.35
    6066  1773.9  6172.7 1785.66  6233.6  1794.5  6267.4 1799.97  6332.8 1814.86
#Mann= 10 ,-1 , 0
    4406     .07       0  4483.9    .035       0  4598.2      .1       0
    4697     .07       0  4963.5     .05       0  4979.6     .07       0
  5094.9    .035       0  5383.9     .07       0  5710.1    .035       0
  5810.6     .07       0
Bank Sta=4963.5,4979.6
XS Rating Curve= 0 ,0
Exp/Cntr=0.3,0.1

Type RM Length L Ch R = 1 ,10787   ,380,380,380
BEGIN DESCRIPTION:
Indian Creek 03 20.0
END DESCRIPTION:
XS GIS Cut Line= 3
      1890475.01     13930325.01        1890875.       13930475.
        1892075.       13930875.
#Sta/Elev= 30
  4564.4 1796.43  4599.2 1792.95  4640.7 1777.02  4698.5  1770.7  4716.8 1761.89
  4743.4 1751.94  4799.2 1745.46  4820.9 1744.91  4890.8 1741.82  4924.9 1743.07
  4964.5 1742.74  5018.7 1735.65  5061.1 1735.49  5061.6 1734.99  5077.2 1735.49
  5078.7 1738.46  5095.5 1740.99  5141.9 1744.48  5250.9  1742.1  5350.4 1738.49
  5383.8 1741.59  5420.8 1741.93  5636.6 1748.53  5790.2 1752.63    5825 1755.01
  5891.4 1765.08  5970.4 1768.77  6065.3  1786.1  6161.9 1798.57  6256.5 1818.13
#Mann= 11 ,-1 , 0
  4564.4     .07       0  4716.8      .1       0  4820.9     .07       0
  4924.9    .035       0  5061.1    .035       0  5077.2    .035       0
  5095.5     .07       0  5250.9    .035       0  5383.8     .07       0
  5420.8    .035       0  5636.6     .07       0
Bank Sta=5061.1,5077.2
XS Rating Curve= 0 ,0
Exp/Cntr=0.3,0.1

Type RM Length L Ch R = 1 ,10407   ,584,584,584
BEGIN DESCRIPTION:
Mapping XS 5e40238b
END DESCRIPTION:
XS GIS Cut Line= 4
      1890078.86     13930666.97      1890845.32     13930826.85
      1891508.78     13930778.15      1891993.64     13930906.28
#Sta/Elev= 30
  4048.1 1810.15  4085.3 1807.07  4185.3 1799.37  4259.3 1794.11  4303.7 1786.24
  4448.7 1772.78  4470.8 1769.41    4641 1756.64  4800.7 1752.62  4810.9 1751.62
  4831.1 1744.21  4850.4 1740.23  4952.7 1737.77  4975.7 1735.47  4976.2 1734.97
  4991.8 1735.47  5112.1 1739.84  5182.3 1738.94  5259.5 1739.08  5298.6 1737.37
  5352.7 1742.21  5388.1  1742.6  5615.1 1750.48  5643.9 1752.98    5764 1764.33
  5788.8 1767.99  5842.7 1780.38  5890.7 1786.39  5892.1 1786.65  5997.8 1801.39
#Mann= 10 ,-1 , 0
  4048.1    .035       0  4085.3     .07       0  4185.3      .1       0
  4448.7    .035       0  4975.7     .05       0  4991.8    .035       0
  5182.3    .035       0  5388.1     .07       0  5890.7      .1       0
  5892.1     .07       0
Bank Sta=4975.7,4991.8
XS Rating Curve= 0 ,0
Exp/Cntr=0.3,0.1

Type RM Length L Ch R = 1 ,9823    ,437,437,437
BEGIN DESCRIPTION:
Indian Creek 03 19.1
END DESCRIPTION:
XS GIS Cut Line= 3
      1890463.32     13931300.49      1891341.57     13931114.16
      1892108.96     13930909.93
#Sta/Elev= 30
  4001.9 1748.53  4132.5 1745.55  4458.2 1740.69  4587.8 1739.88  4739.2 1739.93
    4820 1740.34  4924.8 1737.17  4946.3 1738.22  4988.2 1731.23  4988.7 1730.73
  5004.6 1731.23  5016.2 1731.54    5055 1732.21  5092.2 1736.45  5102.1 1738.59
  5123.3 1738.92  5148.5 1742.56  5253.6 1755.01  5287.8    1765  5309.4 1773.28
    5325 1777.13  5343.7 1778.62  5440.2  1781.4  5446.1 1781.27  5477.2 1786.86
  5520.6 1796.22  5585.8 1803.37  5632.4 1811.18  5660.3 1817.09  5693.8 1828.01
#Mann= 10 ,-1 , 0
  4001.9    .035       0  4132.5     .07       0  4458.2    .035       0
  4587.8     .07       0  4739.2    .035       0  4988.2     .05       0
  5004.6    .035       0  5016.2    .035       0  5148.5      .1       0
  5440.2     .07       0
Bank Sta=4988.2,5004.6
XS Rating Curve= 0 ,0
Exp/Cntr=0.3,0.1

Type RM Length L Ch R = 1 ,9386    ,391,391,391
BEGIN DESCRIPTION:
Indian Creek 03 19.2
END DESCRIPTION:
XS GIS Cut Line= 4
      1890626.36       13931313.      1891338.22     13931389.39
      1891633.35     13931497.03      1891994.46     13931389.39
#Sta/Elev= 30
  4035.7 1744.73    4119 1742.56  4327.1  1739.2    4491 1737.74  4704.4 1736.98
    4768 1742.48  4789.2 1742.61  4859.8 1741.52  4892.9 1743.11  4924.5 1744.17
  4951.1 1743.08  4988.5 1735.49  4995.5 1732.32  4996.1 1730.58  4996.6 1730.08
  5012.5 1730.58  5020.3 1731.22  5049.8  1738.7  5081.7 1746.39  5096.3 1751.55
  5121.4 1753.16  5146.4 1759.76  5215.3 1768.66  5243.5 1769.96  5249.7 1771.91
  5284.2  1775.7    5302 1779.07  5331.1 1789.79  5365.5 1794.36  5442.6 1808.89
#Mann= 11 ,-1 , 0
  4035.7     .07       0    4119    .035       0  4327.1     .07       0
    4491    .035       0  4704.4     .07       0  4789.2      .1       0
  4892.9    .035       0  4996.1     .05       0  5012.5    .035       0
  5049.8    .035       0  5081.7     .07       0
Bank Sta=4996.1,5012.5
XS Rating Curve= 0 ,0
Exp/Cntr=0.3,0.1

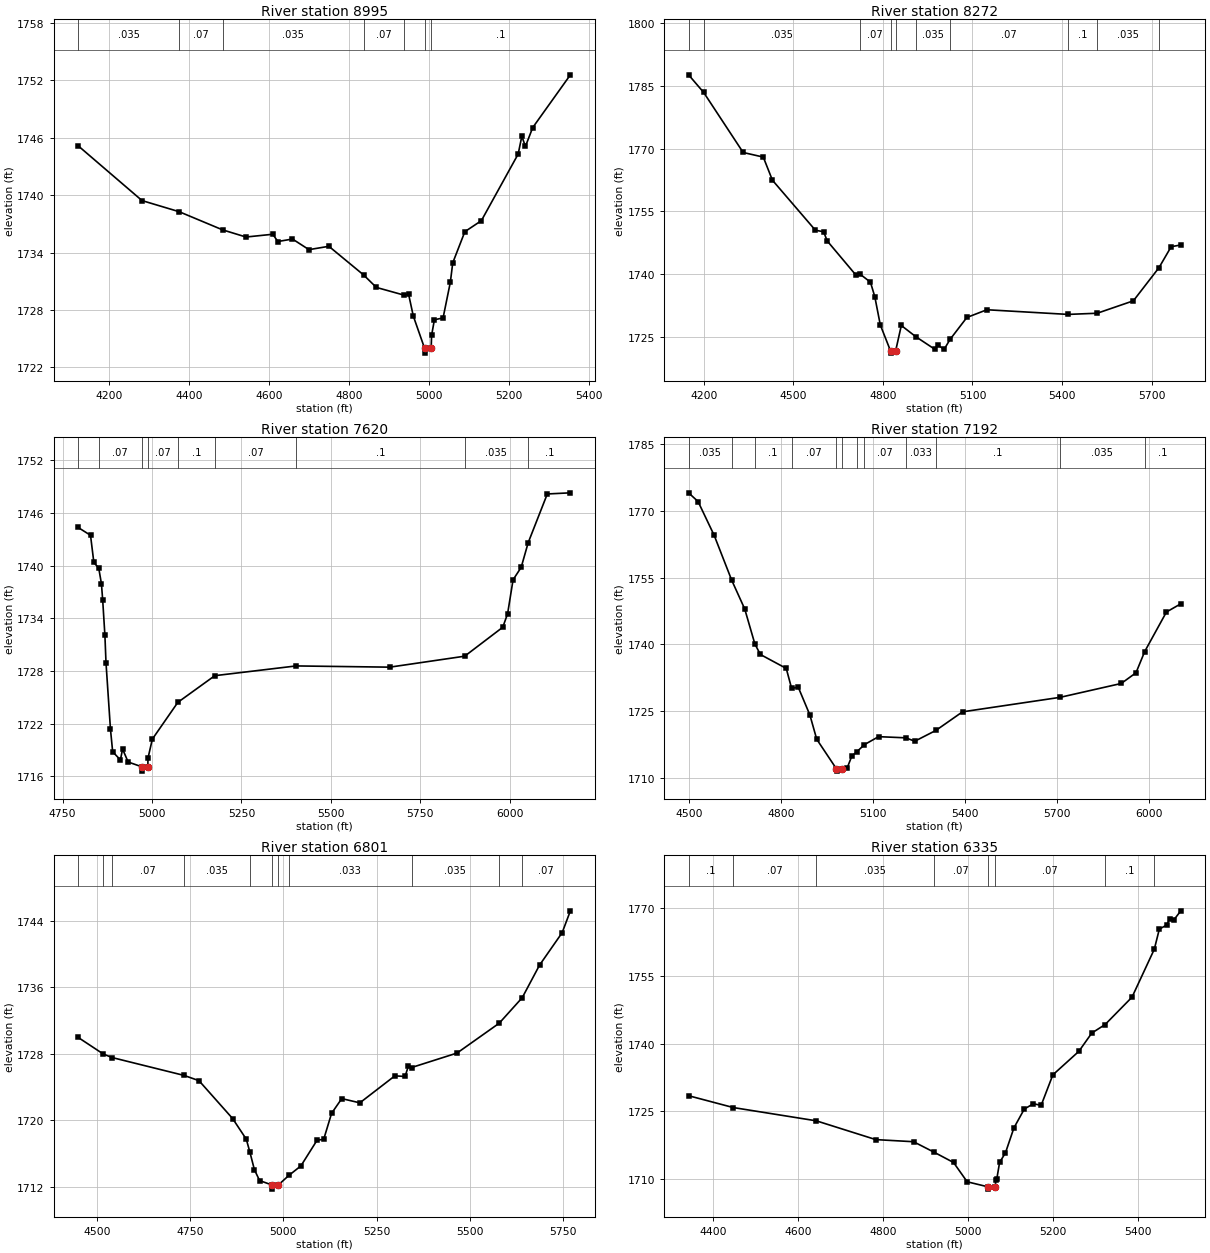
Type RM Length L Ch R = 1 ,8995    ,723,723,723
BEGIN DESCRIPTION:
Indian Creek 03 18.0
END DESCRIPTION:
XS GIS Cut Line= 3
      1890479.72     13931487.86        1891325.       13931725.
      1891674.93     13931675.01
#Sta/Elev= 30
  4121.7 1745.16  4281.5 1739.43  4374.2 1738.27    4483 1736.37  4541.6 1735.62
  4608.7 1735.91  4621.2 1735.15  4657.9 1735.41  4699.1  1734.3  4748.9 1734.65
  4835.9 1731.65  4867.7 1730.35  4937.4 1729.54  4948.3 1729.65  4960.1 1727.36
  4988.4 1723.98  4988.9 1723.48  5004.8 1723.98  5005.9 1725.34  5012.9 1726.97
  5034.6 1727.16  5052.8  1730.9  5058.8 1732.92  5089.1 1736.18  5130.4 1737.33
  5222.5  1744.3  5231.6 1746.16  5240.6 1745.09  5258.8 1747.06  5353.1 1752.58
#Mann= 7 ,-1 , 0
  4121.7    .035       0  4374.2     .07       0    4483    .035       0
  4835.9     .07       0  4937.4      .1       0  4988.4     .05       0
  5004.8      .1       0
Bank Sta=4988.4,5004.8
XS Rating Curve= 0 ,0
Exp/Cntr=0.3,0.1

Type RM Length L Ch R = 1 ,8272    ,652,652,652
BEGIN DESCRIPTION:
Indian Creek 03 17.1
END DESCRIPTION:
XS GIS Cut Line= 4
      1890190.43     13932460.87      1890909.02     13932315.34
      1891210.99     13932261.36      1891529.14     13931742.81
#Sta/Elev= 30
  4149.3 1787.57  4199.9 1783.37  4332.1 1769.06  4399.5 1767.96  4430.1 1762.45
  4573.9 1750.53  4601.5 1750.16  4613.7 1747.96  4709.4 1739.86  4721.9 1740.15
  4758.3 1738.15  4772.9 1734.69  4791.3 1727.97  4825.7 1721.73  4826.2 1721.23
  4842.6 1721.73  4861.7 1727.82  4909.8 1725.17  4974.5 1722.12  4983.6  1723.2
    5005 1722.12  5024.9  1724.5  5081.2 1729.73  5148.2 1731.57  5419.8 1730.46
  5517.7 1730.74  5638.8  1733.7  5724.5  1741.6  5765.3  1746.6  5797.6 1747.01
#Mann= 10 ,-1 , 0
  4149.3     .07       0  4199.9    .035       0  4721.9     .07       0
  4825.7    .035       0  4842.6     .07       0  4909.8    .035       0
  5024.9     .07       0  5419.8      .1       0  5517.7    .035       0
  5724.5      .1       0
Bank Sta=4825.7,4842.6
XS Rating Curve= 0 ,0
Exp/Cntr=0.3,0.1

Type RM Length L Ch R = 1 ,7620    ,428,428,428
BEGIN DESCRIPTION:
Indian Creek 03 17.0
END DESCRIPTION:
XS GIS Cut Line= 3
        1890975.       13932875.        1891175.       13932825.
      1891574.99     13931725.02
#Sta/Elev= 30
  4793.4 1744.36    4828 1743.47  4837.3 1740.37    4851 1739.72  4858.5 1737.95
  4862.1 1736.04  4868.2 1732.07  4871.3 1728.93  4883.7  1721.4  4889.9  1718.8
  4911.5 1717.87  4917.7  1719.1  4933.2 1717.63  4971.1 1717.09  4971.6 1716.59
  4988.1 1717.09  4988.8 1718.09  5000.9 1720.24  5072.2 1724.43  5175.6 1727.47
  5403.1 1728.58  5664.9 1728.44  5874.4 1729.69  5980.9 1732.99  5994.4 1734.53
  6009.7  1738.4  6032.4 1739.82  6051.9 1742.62  6105.4 1748.18    6170 1748.31
#Mann= 9 ,-1 , 0
  4793.4    .035       0    4851     .07       0  4971.1     .05       0
  4988.1     .07       0  5072.2      .1       0  5175.6     .07       0
  5403.1      .1       0  5874.4    .035       0  6051.9      .1       0
Bank Sta=4971.1,4988.1
XS Rating Curve= 0 ,0
Exp/Cntr=0.3,0.1

Type RM Length L Ch R = 1 ,7192    ,391,391,391
BEGIN DESCRIPTION:
Indian Creek 03 16.0
END DESCRIPTION:
XS GIS Cut Line= 3
        1891475.     13933375.03        1891525.       13932875.
        1891625.     13931774.96
#Sta/Elev= 30
  4498.2    1774  4529.2 1772.05    4582 1764.43  4639.1 1754.39  4681.5 1747.96
  4714.7  1740.1  4732.7 1737.74  4817.1 1734.62  4834.6 1730.15  4856.3  1730.4
  4894.3 1724.17  4916.6 1718.73  4981.1 1712.08  4981.6 1711.58  4998.2 1712.08
  5016.1 1712.31  5031.2 1714.95    5047 1715.89  5072.6 1717.53  5118.5 1719.31
  5207.2 1719.05  5236.8 1718.29  5305.7 1720.71  5392.6 1724.88  5711.3 1728.13
  5910.8 1731.24    5959 1733.64  5987.4  1738.4  6058.4 1747.27  6105.3 1749.11
#Mann= 12 ,-1 , 0
  4498.2    .035       0  4639.1     .07       0  4714.7      .1       0
  4834.6     .07       0  4981.1     .05       0  4998.2     .07       0
    5047      .1       0  5072.6     .07       0  5207.2    .033       0
  5305.7      .1       0  5711.3    .035       0  5987.4      .1       0
Bank Sta=4981.1,4998.2
XS Rating Curve= 0 ,0
Exp/Cntr=0.3,0.1

Type RM Length L Ch R = 1 ,6801    ,466,466,466
BEGIN DESCRIPTION:
Indian Creek 03 15.0
END DESCRIPTION:
XS GIS Cut Line= 4
      1891828.77     13933057.72      1891843.96     13932615.03
      1891674.69     13932547.75      1891774.51     13931859.87
#Sta/Elev= 30
  4449.8 1729.99  4517.7 1727.98  4541.7 1727.56  4733.8 1725.42  4773.8 1724.79
  4864.1 1720.23  4900.7 1717.75  4910.3 1716.21  4922.5 1714.08  4936.4 1712.77
  4969.6 1712.24  4970.1 1711.74  4986.7 1712.24    5015 1713.39  5047.3 1714.54
  5090.8 1717.64  5108.3 1717.72  5129.5 1720.86  5156.8 1722.63  5205.3 1722.12
  5299.3 1725.37  5326.6 1725.29  5335.7 1726.58  5344.1 1726.37    5466 1728.11
  5579.1  1731.7  5640.8 1734.77  5687.3 1738.69  5747.9 1742.59    5770 1745.22
#Mann= 11 ,-1 , 0
  4449.8    .035       0  4517.7      .1       0  4541.7     .07       0
  4733.8    .035       0  4910.3      .1       0  4969.6     .05       0
  4986.7      .1       0    5015    .033       0  5344.1    .035       0
  5579.1      .1       0  5640.8     .07       0
Bank Sta=4969.6,4986.7
XS Rating Curve= 0 ,0
Exp/Cntr=0.3,0.1

Type RM Length L Ch R = 1 ,6335    ,408,408,408
BEGIN DESCRIPTION:
Indian Creek 03 14.0
END DESCRIPTION:
XS GIS Cut Line= 3
      1891874.99     13933025.02        1892125.       13932425.
        1892225.     13931925.02
#Sta/Elev= 30
  4341.5 1728.42    4447 1725.79  4642.4 1722.85  4782.7 1718.68  4871.6 1718.21
  4920.7 1715.85  4965.9  1713.6    4998 1709.32  5047.5 1708.19    5048 1707.69
  5064.7 1708.19  5065.1 1709.73  5067.9    1710  5074.4 1713.61  5088.3 1715.76
  5108.1 1721.27  5132.6 1725.46    5154 1726.64  5172.3 1726.28  5199.9 1733.05
  5261.1 1738.26  5291.7 1742.33    5323 1744.21  5386.5  1750.3    5439 1760.94
  5450.8 1765.39  5468.2  1766.3  5475.2 1767.68  5484.4 1767.36  5501.4 1769.45
#Mann= 8 ,-1 , 0
  4341.5      .1       0    4447     .07       0  4642.4    .035       0
  4920.7     .07       0  5047.5     .05       0  5064.7     .07       0
    5323      .1       0    5439    .035       0
Bank Sta=5047.5,5064.7
XS Rating Curve= 0 ,0
Exp/Cntr=0.3,0.1