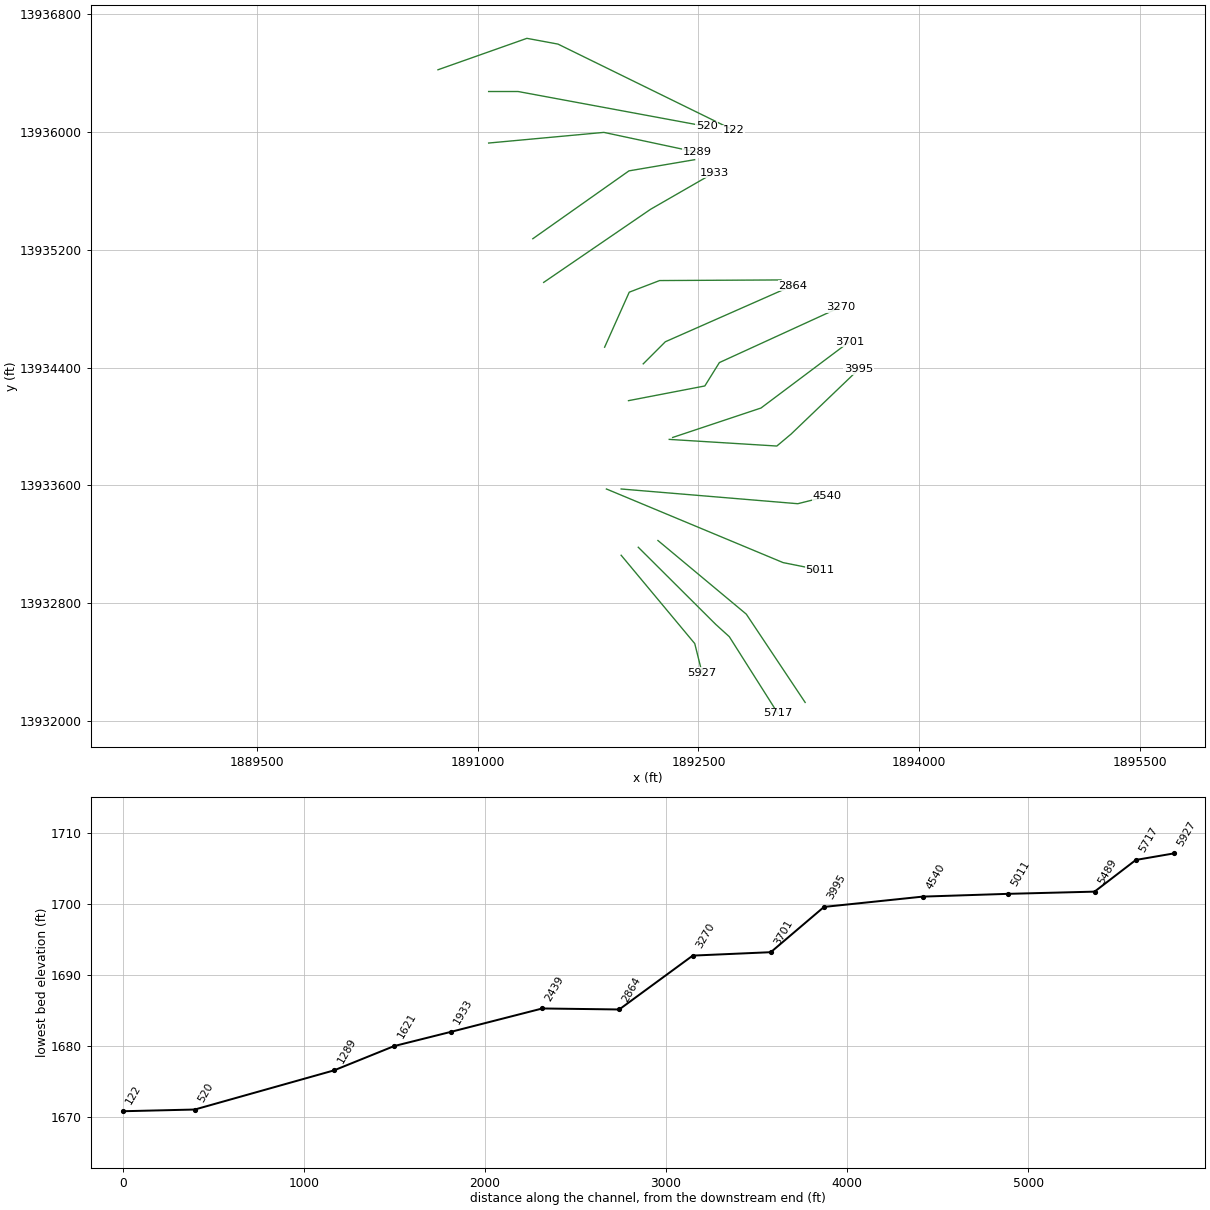
HEC-RAS study Indian Creek 03.prj: Indian Creek 03 Base Level Engineering

--- Indian Creek 03.g01 (geometry) --- (continued)

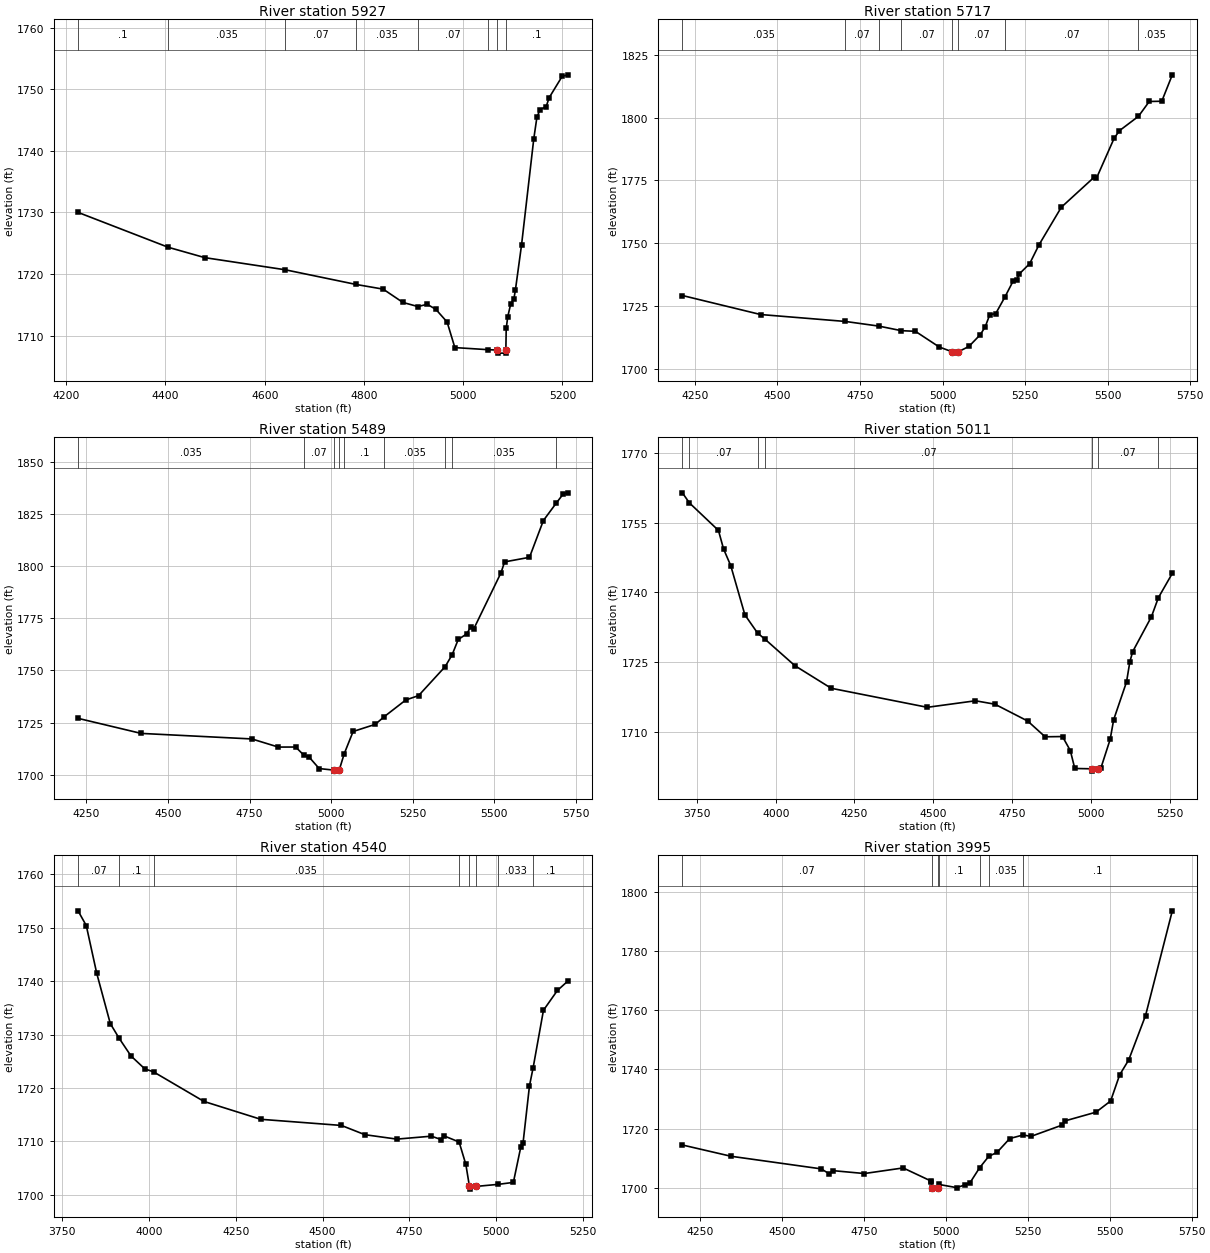
Type RM Length L Ch R = 1 ,5927    ,210,210,210
BEGIN DESCRIPTION:
Indian Creek 03 13.0
END DESCRIPTION:
XS GIS Cut Line= 3
      1891975.01     13933124.99        1892475.       13932525.
      1892525.01     13932324.97
#Sta/Elev= 30
  4223.8 1729.99  4405.7 1724.32  4479.3 1722.64  4641.4 1720.67    4784 1718.29
  4838.6 1717.53  4878.4 1715.37  4908.7  1714.7  4927.4 1715.07  4944.8 1714.25
  4967.5 1712.19  4983.1 1708.04    5050  1707.7  5068.6 1707.64  5069.1 1707.14
  5085.4 1707.14  5085.9 1707.64  5086.6 1711.15  5089.7 1713.05  5095.8 1715.17
    5102 1715.93  5105.1 1717.37  5117.5 1724.71  5142.2 1741.97  5148.4  1745.4
  5154.8 1746.68    5167 1747.14  5173.2 1748.62  5199.4 1752.08    5211 1752.32
#Mann= 8 ,-1 , 0
  4223.8      .1       0  4405.7    .035       0  4641.4     .07       0
    4784    .035       0  4908.7     .07       0    5050      .1       0
  5068.6     .05       0  5085.9      .1       0
Bank Sta=5068.6,5085.9
XS Rating Curve= 0 ,0
Exp/Cntr=0.3,0.1

Type RM Length L Ch R = 1 ,5717    ,228,228,228
BEGIN DESCRIPTION:
Indian Creek 03 12.1
END DESCRIPTION:
XS GIS Cut Line= 4
      1892091.35     13933179.27      1892616.53     13932656.26
      1892709.84     13932571.62      1893039.72     13932050.76
#Sta/Elev= 30
  4212.2 1729.16    4449 1721.59  4705.9 1718.83  4807.2 1716.98  4875.3 1715.16
  4917.8 1714.91  4989.9 1708.67  5029.9 1706.72  5030.4 1706.22  5047.2 1706.72
  5079.9 1708.88  5113.9  1713.5    5129 1716.59  5143.2 1721.57    5161 1721.94
  5188.9 1728.55  5214.2    1735  5224.8 1735.41    5232 1737.68  5263.9 1741.84
  5292.3 1749.37  5359.8 1764.31  5460.2 1776.38  5466.3 1775.88  5519.6 1791.73
  5535.7 1794.78  5593.4 1800.51  5626.1 1806.42    5664 1806.51  5695.9 1817.03
#Mann= 8 ,-1 , 0
  4212.2    .035       0  4705.9     .07       0  4807.2    .035       0
  4875.3     .07       0  5029.9     .05       0  5047.2     .07       0
  5188.9     .07       0  5593.4    .035       0
Bank Sta=5029.9,5047.2
XS Rating Curve= 0 ,0
Exp/Cntr=0.3,0.1

Type RM Length L Ch R = 1 ,5489    ,478,478,478
BEGIN DESCRIPTION:
Indian Creek 03 12.0
END DESCRIPTION:
XS GIS Cut Line= 3
      1892225.03     13933224.98        1892825.       13932725.
        1893225.       13932125.
#Sta/Elev= 30
  4224.1 1727.06  4417.5 1719.84  4757.2 1717.18  4838.2 1713.29  4891.4 1713.31
    4917 1709.32    4933 1708.43  4963.4 1702.99  5007.6 1702.26  5008.1 1701.76
  5024.9 1702.26  5040.2 1710.08  5067.5 1720.76  5135.3 1724.17  5163.1 1727.88
    5229 1735.86  5268.2 1737.95  5349.8 1751.86  5371.2 1757.56  5389.8 1764.85
  5416.5 1767.61  5428.3 1771.06    5437 1769.79  5521.1 1796.89  5531.9 1802.04
  5608.3 1804.23  5650.9 1821.87  5691.1 1830.37  5712.1 1834.66  5726.2 1835.14
#Mann= 9 ,-1 , 0
  4224.1    .035       0    4917     .07       0  5007.6     .05       0
  5024.9     .07       0  5040.2      .1       0  5163.1    .035       0
  5349.8     .07       0  5371.2    .035       0  5691.1     .07       0
Bank Sta=5007.6,5024.9
XS Rating Curve= 0 ,0
Exp/Cntr=0.3,0.1

Type RM Length L Ch R = 1 ,5011    ,471,471,471
BEGIN DESCRIPTION:
Indian Creek 03 11.0
END DESCRIPTION:
XS GIS Cut Line= 3
      1891874.97     13933575.01        1893075.       13933075.
      1893324.92     13933025.02
#Sta/Elev= 30
  3703.9  1761.5  3726.1 1759.33  3818.3 1753.39  3834.6 1749.38  3857.3  1745.8
  3902.3 1735.16  3942.6 1731.23  3965.2 1729.97    4061  1724.2  4176.2 1719.33
  4481.3 1715.22  4634.1 1716.63  4695.8 1715.89  4799.8 1712.26  4855.1 1708.86
  4910.3 1708.91  4935.1 1705.88  4949.3 1702.02  5004.4 1701.95  5004.9 1701.45
    5022 1701.95  5032.1  1702.1  5061.6 1708.31  5072.7 1712.55  5113.5 1720.69
  5124.1 1725.06  5133.1 1727.24  5192.5 1734.76  5214.5 1738.86  5258.8 1744.12
#Mann= 7 ,-1 , 0
  3703.9    .035       0  3726.1     .07       0  3942.6      .1       0
  3965.2     .07       0  5004.4     .05       0    5022     .07       0
  5214.5    .035       0
Bank Sta=5004.4,5022
XS Rating Curve= 0 ,0
Exp/Cntr=0.3,0.1

Type RM Length L Ch R = 1 ,4540    ,545,545,545
BEGIN DESCRIPTION:
Indian Creek 03 10.0
END DESCRIPTION:
XS GIS Cut Line= 3
      1891975.04       13933575.        1893175.       13933475.
      1893375.02     13933525.01
#Sta/Elev= 30
    3796 1753.15  3819.7 1750.39  3849.8 1741.46  3888.9 1732.04  3914.1 1729.32
  3948.5 1725.98  3988.2 1723.57  4013.3 1723.01  4158.6 1717.47    4322 1714.13
  4554.2 1712.98  4621.7 1711.25  4713.7 1710.42  4813.1 1710.97  4841.7 1710.33
  4849.2 1711.04    4893 1709.88  4912.4 1705.68  4922.8 1701.56  4923.3 1701.06
  4940.4 1701.56  5005.3 1701.95  5049.2 1702.32  5070.8 1709.02    5077 1709.67
  5095.6 1720.42  5106.1 1723.79  5135.8 1734.54    5176 1738.25  5206.3 1740.02
#Mann= 8 ,-1 , 0
    3796     .07       0  3914.1      .1       0  4013.3    .035       0
    4893     .07       0  4922.8     .05       0  4940.4     .07       0
  5005.3    .033       0  5106.1      .1       0
Bank Sta=4922.8,4940.4
XS Rating Curve= 0 ,0
Exp/Cntr=0.3,0.1

Type RM Length L Ch R = 1 ,3995    ,294,294,294
BEGIN DESCRIPTION:
Indian Creek 03 8.1
END DESCRIPTION:
XS GIS Cut Line= 4
      1892301.72      13933911.9       1893032.6     13933866.76
      1893129.82     13933948.36      1893588.14     13934387.58
#Sta/Elev= 30
    4197  1714.5  4345.1  1710.7  4620.6 1706.44  4644.7 1704.77  4656.8 1705.84
  4751.9 1704.87  4870.2 1706.76  4954.1  1702.4  4956.2 1702.09  4957.8 1700.11
  4958.3 1699.61  4975.5 1700.11  4978.5 1701.21  5033.4 1700.11  5058.4 1701.03
    5074 1701.74  5103.3 1706.81  5131.4 1710.69  5156.4    1712  5195.3 1716.68
  5235.8 1717.87  5260.3 1717.41  5355.9 1721.25  5362.9  1722.6  5458.4 1725.58
  5502.9 1729.35  5530.4 1738.14  5558.1  1743.2  5609.4 1758.17    5691  1793.5
#Mann= 7 ,-1 , 0
    4197     .07       0  4957.8     .05       0  4975.5     .07       0
  4978.5      .1       0  5103.3     .07       0  5131.4    .035       0
  5235.8      .1       0
Bank Sta=4957.8,4975.5
XS Rating Curve= 0 ,0
Exp/Cntr=0.3,0.1

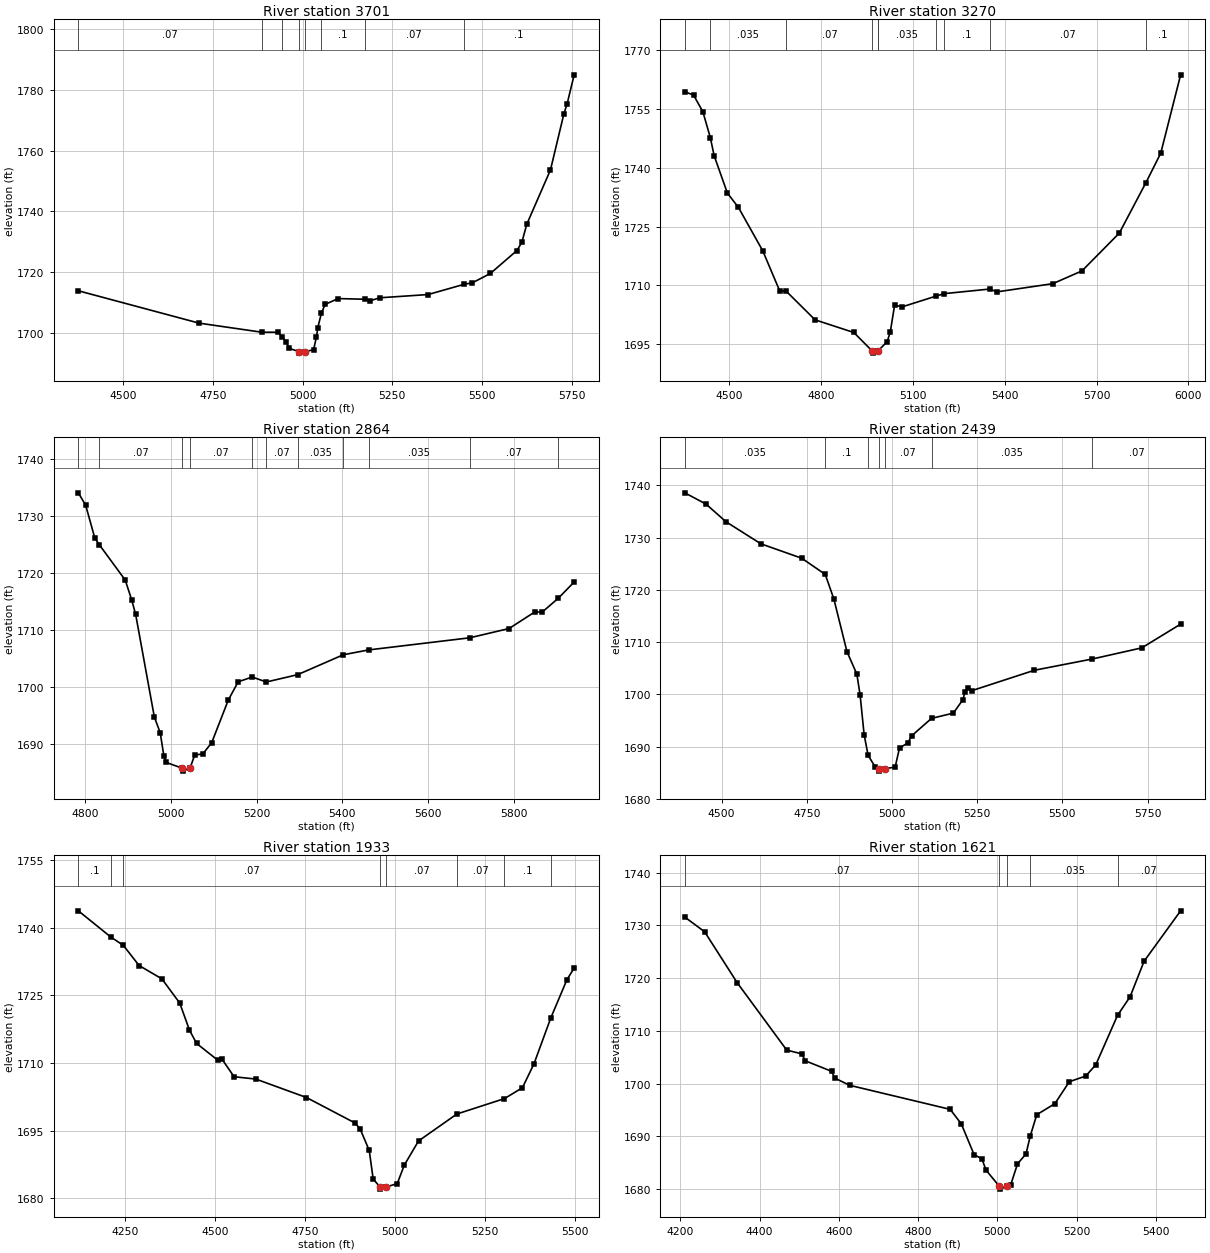
Type RM Length L Ch R = 1 ,3701    ,431,431,431
BEGIN DESCRIPTION:
Indian Creek 03 8.0
END DESCRIPTION:
XS GIS Cut Line= 3
        1892325.       13933925.        1892925.       13934125.
      1893525.03     13934575.02
#Sta/Elev= 30
  4374.7 1713.79  4711.2 1703.13  4886.4 1700.13  4932.5 1700.13  4942.9 1698.55
  4954.9 1696.91    4962 1694.84  4990.1 1693.74  4990.6 1693.24  5007.8 1693.74
  5030.6 1694.37  5038.7 1698.58  5042.4 1701.62  5052.3 1706.36  5062.8 1709.31
  5099.2 1711.22  5172.7 1711.01  5188.7 1710.51  5214.9 1711.48  5349.9 1712.55
  5449.6  1715.9  5473.7 1716.44  5523.5 1719.49  5597.4 1727.04  5611.3 1729.73
  5624.9 1735.67  5691.2 1753.66  5728.7 1772.18  5737.8 1775.51  5757.2 1784.98
#Mann= 8 ,-1 , 0
  4374.7     .07       0  4886.4      .1       0  4942.9    .035       0
  4990.1    .035       0  5007.8    .035       0  5052.3      .1       0
  5172.7     .07       0  5449.6      .1       0
Bank Sta=4990.1,5007.8
XS Rating Curve= 0 ,0
Exp/Cntr=0.3,0.1

Type RM Length L Ch R = 1 ,3270    ,406,406,406
BEGIN DESCRIPTION:
Indian Creek 03 7.0
END DESCRIPTION:
XS GIS Cut Line= 4
      1892025.04     13934175.01      1892543.38     13934274.84
      1892642.34     13934433.69       1893465.3     13934810.62
#Sta/Elev= 30
  4354.6 1759.38  4383.3 1758.54  4413.8 1754.26  4438.1 1747.66  4450.5 1743.09
  4493.6 1733.58  4529.9 1729.89  4609.4 1718.83  4664.4 1708.68  4686.7 1708.49
  4780.4 1701.24  4906.9 1698.02  4967.6 1693.26  4968.1 1692.76  4985.4 1693.26
  4986.2 1693.34  5015.8 1695.69    5026 1698.12  5040.1 1704.95  5065.9 1704.58
  5175.8  1707.3  5201.8 1707.92  5350.5 1709.09  5375.2 1708.38    5557 1710.46
  5652.4 1713.72  5774.5 1723.36  5860.7 1736.11  5909.8 1743.71  5974.8  1763.7
#Mann= 10 ,-1 , 0
  4354.6     .07       0  4438.1    .035       0  4686.7     .07       0
  4967.6    .035       0  4985.4     .07       0  4986.2    .035       0
  5175.8     .07       0  5201.8      .1       0  5350.5     .07       0
  5860.7      .1       0
Bank Sta=4967.6,4985.4
XS Rating Curve= 0 ,0
Exp/Cntr=0.3,0.1

Type RM Length L Ch R = 1 ,2864    ,425,425,425
BEGIN DESCRIPTION:
Indian Creek 03 6.0
END DESCRIPTION:
XS GIS Cut Line= 3
      1892125.03     13934425.03        1892275.       13934575.
      1893139.52      13934956.4
#Sta/Elev= 30
    4784 1734.02  4801.2 1731.83  4822.4 1726.08  4832.6 1724.95  4893.4 1718.71
  4908.3 1715.29  4917.8 1712.67  4961.3 1694.71  4975.2 1691.87  4983.6 1687.83
  4988.9 1686.71  5026.8 1685.68  5027.3 1685.18  5044.6 1685.68  5055.3 1687.96
    5075 1688.24  5095.3 1690.19  5133.9 1697.65    5157 1700.85  5189.7  1701.7
  5222.6 1700.82  5295.9 1702.11  5402.2  1705.6  5461.3 1706.45  5697.6 1708.58
  5789.3 1710.21  5848.8  1713.1  5866.6  1713.1  5904.4 1715.55    5941 1718.37
#Mann= 11 ,-1 , 0
    4784    .035       0  4832.6     .07       0  5026.8     .05       0
  5044.6     .07       0  5189.7    .035       0  5222.6     .07       0
  5295.9    .035       0  5402.2     .07       0  5461.3    .035       0
  5697.6     .07       0  5904.4    .035       0
Bank Sta=5026.8,5044.6
XS Rating Curve= 0 ,0
Exp/Cntr=0.3,0.1

Type RM Length L Ch R = 1 ,2439    ,506,506,506
BEGIN DESCRIPTION:
Indian Creek 03 5.0
END DESCRIPTION:
XS GIS Cut Line= 4
      1891862.78     13934538.17      1892029.99     13934911.83
      1892236.41     13934990.89      1893061.19     13934995.01
#Sta/Elev= 30
    4392 1738.56  4454.2 1736.41    4513 1733.02  4615.2 1728.81  4735.5 1726.04
  4804.2 1722.95  4829.4 1718.27    4868 1708.16  4896.9 1703.89  4906.5  1699.9
  4918.3 1692.31  4929.9 1688.36  4951.5 1686.04  4961.8 1685.82  4962.3 1685.32
  4979.7 1685.82  5009.3 1686.07  5022.2 1689.77  5046.2 1690.68  5058.2  1692.1
  5116.1 1695.41  5180.2 1696.42  5208.2 1698.99  5214.2 1700.44  5223.2 1701.29
  5235.2 1700.73  5418.2 1704.62  5587.9 1706.77  5733.2  1708.9  5847.2 1713.44
#Mann= 7 ,-1 , 0
    4392    .035       0  4804.2      .1       0  4929.9     .07       0
  4961.8     .05       0  4979.7     .07       0  5116.1    .035       0
  5587.9     .07       0
Bank Sta=4961.8,4979.7
XS Rating Curve= 0 ,0
Exp/Cntr=0.3,0.1

Type RM Length L Ch R = 1 ,1933    ,312,312,312
BEGIN DESCRIPTION:
Indian Creek 03 4.0
END DESCRIPTION:
XS GIS Cut Line= 3
      1891448.79     13934978.29        1892175.       13935475.
      1892606.82      13935723.6
#Sta/Elev= 30
  4119.7 1743.75  4209.8 1737.95  4244.8 1736.09  4288.6 1731.62  4351.9 1728.66
  4401.6 1723.29  4428.5  1717.3  4448.5 1714.33  4508.2 1710.56  4518.1 1710.95
  4552.6 1706.95  4613.1 1706.43  4753.8 1702.34  4888.3 1696.71  4902.8  1695.4
  4928.2 1690.61  4939.2 1684.26    4958 1682.52  4958.5 1682.02  4976.1 1682.52
    5006 1683.24  5025.8 1687.36  5065.3 1692.71  5171.8 1698.68  5304.1  1702.1
    5354 1704.51  5386.1 1709.81  5432.7 1719.96  5477.8 1728.49  5497.8 1731.06
#Mann= 8 ,-1 , 0
  4119.7      .1       0  4209.8    .035       0  4244.8     .07       0
    4958    .035       0  4976.1     .07       0  5171.8     .07       0
  5304.1      .1       0  5432.7     .07       0
Bank Sta=4958,4976.1
XS Rating Curve= 0 ,0
Exp/Cntr=0.3,0.1

Type RM Length L Ch R = 1 ,1621    ,332,332,332
BEGIN DESCRIPTION:
Indian Creek 03 3.0
END DESCRIPTION:
XS GIS Cut Line= 3
        1891375.       13935275.      1892028.09     13935735.91
      1892474.22     13935811.83
#Sta/Elev= 30
    4211 1731.56  4261.1 1728.78  4343.4 1719.12  4468.3 1706.37  4506.5 1705.65
  4515.1 1704.34  4581.9 1702.34  4589.5 1701.07  4627.1  1699.7  4881.1 1695.14
  4909.1  1692.4  4941.4 1686.57  4961.3 1685.76  4971.3 1683.66  5005.5 1680.53
    5006 1680.03  5023.6 1680.53  5033.6 1680.78    5051  1684.8  5072.6 1686.72
  5083.3 1690.11  5099.7 1694.13  5145.4 1696.22  5181.9 1700.38  5223.5 1701.46
  5248.8  1703.6  5303.6 1712.95  5335.3 1716.47  5370.6  1723.2  5462.9 1732.75
#Mann= 5 ,-1 , 0
    4211     .07       0  5005.5     .05       0  5023.6     .07       0
  5083.3    .035       0  5303.6     .07       0
Bank Sta=5005.5,5023.6
XS Rating Curve= 0 ,0
Exp/Cntr=0.3,0.1

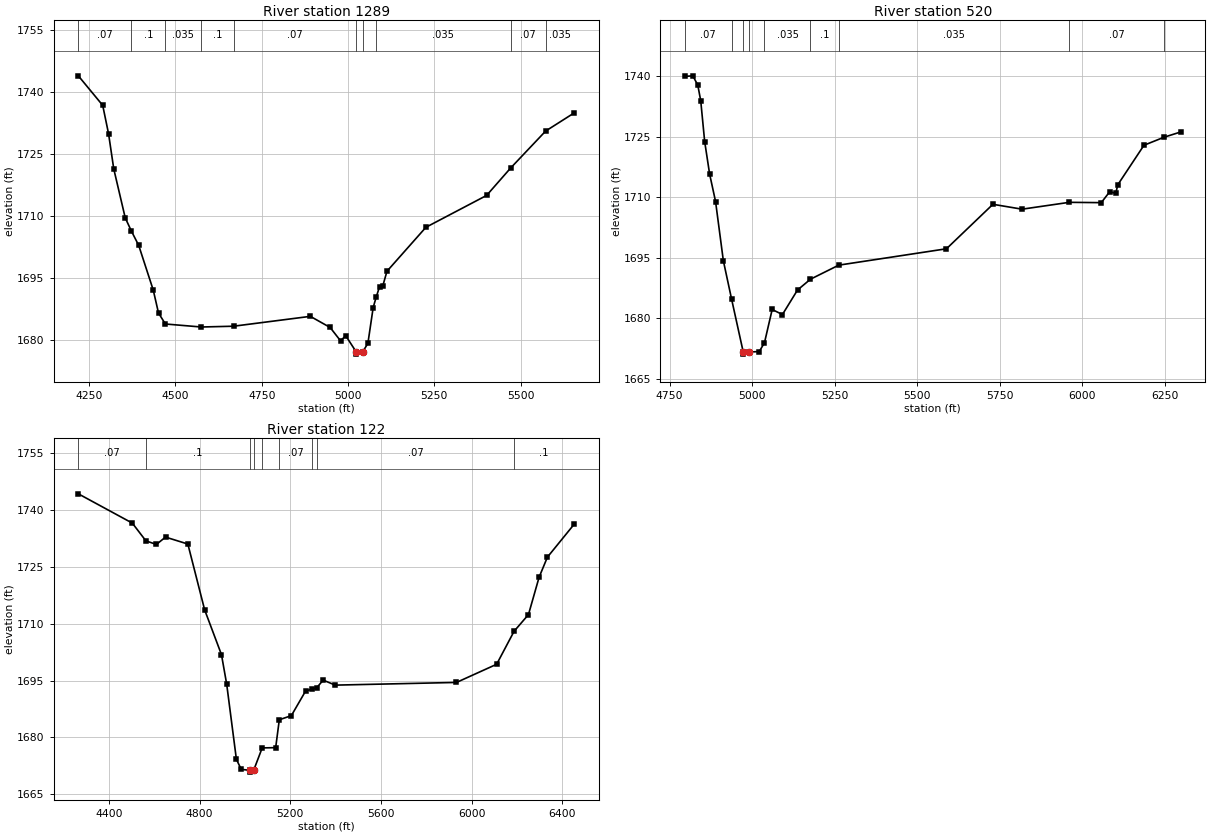
Type RM Length L Ch R = 1 ,1289    ,769,769,769
BEGIN DESCRIPTION:
Indian Creek 03 2.0
END DESCRIPTION:
XS GIS Cut Line= 3
      1891075.01       13935925.      1891857.73     13935997.31
      1892493.49     13935861.77
#Sta/Elev= 30
  4218.9 1744.02  4289.5 1736.87  4306.5 1729.97  4321.5 1721.48  4354.7 1709.63
  4372.2 1706.48  4393.8 1702.94    4436 1692.09  4451.1 1686.57    4471 1683.91
    4575 1683.18  4668.4 1683.37  4890.9 1685.76  4948.2 1683.07  4978.3 1679.84
  4993.4 1681.07    5024 1677.11  5024.5 1676.61  5042.1 1677.11  5057.6 1679.22
  5072.9  1687.9  5081.7 1690.44  5091.3 1692.93  5100.5 1693.06  5112.8 1696.68
  5225.6 1707.33  5401.4 1715.05  5470.9 1721.68  5572.4 1730.64    5655 1735.03
#Mann= 10 ,-1 , 0
  4218.9     .07       0  4372.2      .1       0    4471    .035       0
    4575      .1       0  4668.4     .07       0    5024     .05       0
  5042.1     .07       0  5081.7    .035       0  5470.9     .07       0
  5572.4    .035       0
Bank Sta=5024,5042.1
XS Rating Curve= 0 ,0
Exp/Cntr=0.3,0.1

Type RM Length L Ch R = 1 ,520     ,398,398,398
BEGIN DESCRIPTION:
Indian Creek 03 1.0
END DESCRIPTION:
XS GIS Cut Line= 3
      1891075.03       13936275.        1891275.       13936275.
      1892555.42     13936037.65
#Sta/Elev= 30
  4796.1 1739.93  4820.3 1740.07  4835.3 1737.81  4844.3 1733.95  4856.3 1723.79
  4871.3 1715.73  4889.3 1708.92  4912.9 1694.24    4938 1684.68  4973.2  1671.6
  4973.7  1671.1  4991.3  1671.6  5021.7 1671.75  5037.5 1673.92  5060.8 1682.16
  5091.9 1680.91  5137.6 1686.99  5176.9 1689.67  5262.5 1693.15  5588.9 1697.21
  5729.6 1708.23    5818 1707.02  5961.1 1708.72  6057.9 1708.64  6083.6 1711.36
  6101.8 1710.94  6107.9 1713.07  6187.2 1722.86  6247.9 1724.85  6298.3 1726.15
#Mann= 9 ,-1 , 0
  4796.1     .07       0    4938      .1       0  4973.2     .05       0
  4991.3      .1       0  5037.5    .035       0  5176.9      .1       0
  5262.5    .035       0  5961.1     .07       0  6247.9      .1       0
Bank Sta=4973.2,4991.3
XS Rating Curve= 0 ,0
Exp/Cntr=0.3,0.1

Type RM Length L Ch R = 1 ,122     ,0,0,0
BEGIN DESCRIPTION:
Indian Creek 03 0.0
END DESCRIPTION:
XS GIS Cut Line= 4
      1890730.73     13936422.68      1891334.86     13936636.21
       1891545.8     13936597.14      1892741.13      13936011.2
#Sta/Elev= 30
  4265.3 1744.24  4503.3 1736.52  4563.4 1731.83  4609.7  1730.9  4649.7 1732.83
  4748.3    1731  4822.2 1713.67  4896.5 1701.84  4919.6 1694.03  4962.3 1674.25
  4983.7 1671.58  5020.4 1671.36  5020.9 1670.86  5038.6 1671.36  5076.1 1677.25
  5135.5 1677.31  5151.6 1684.67  5204.6 1685.75    5268 1692.29  5294.5 1692.69
  5316.8 1693.12  5344.9 1695.12  5398.3  1693.8  5932.9 1694.51    6110  1699.3
  6186.9    1708  6250.3  1712.4  6297.1 1722.23  6333.8 1727.54  6451.8 1736.22
#Mann= 9 ,-1 , 0
  4265.3     .07       0  4563.4      .1       0  5020.4     .05       0
  5038.6      .1       0  5076.1    .035       0  5151.6     .07       0
  5294.5      .1       0  5316.8     .07       0  6186.9      .1       0
Bank Sta=5020.4,5038.6
XS Rating Curve= 0 ,0
Exp/Cntr=0.3,0.1

Chan Stop Cuts=-1
Use User Specified Reach Order=0
Composite Channel Slope=5