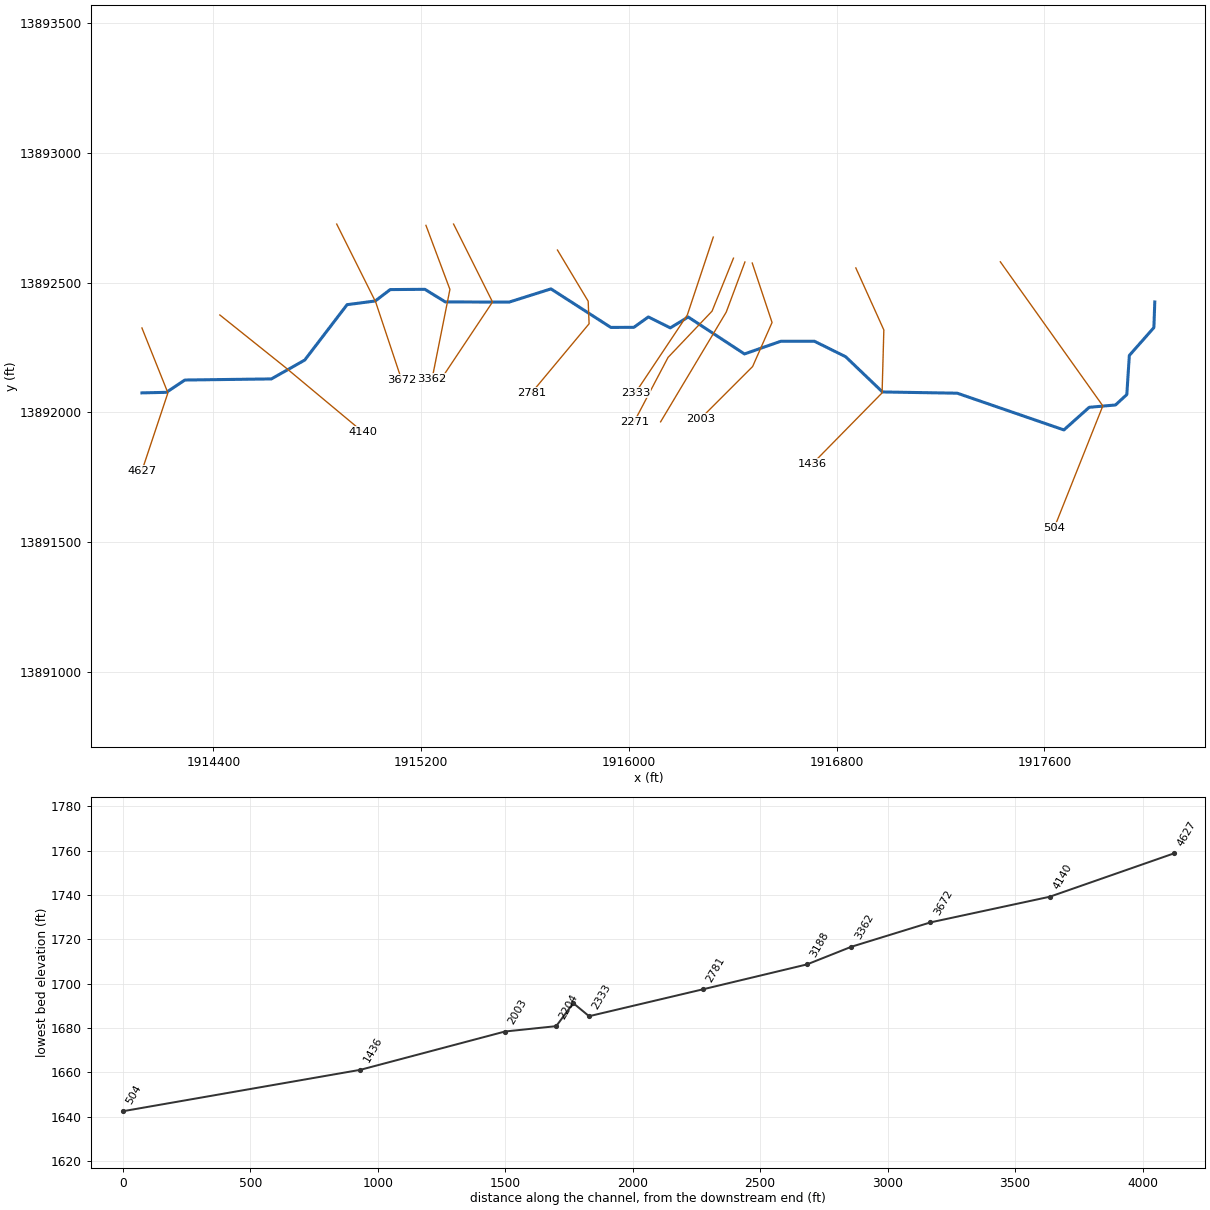
--- Indian Creek 04.prj (project) ---

Proj Title=Indian Creek 04 Base Level Engineering
Current Plan=p01
Default Exp/Contr=0.3,0.1
English Units
Geom File=g01
Flow File=f01
Plan File=p01
Y Axis Title=Elevation
X Axis Title(PF)=Main Channel Distance
X Axis Title(XS)=Station
BEGIN DESCRIPTION:
Indian Creek 04
END DESCRIPTION:
DSS Export Rating Curves= 0
DSS Export Rating Curve Sorted= 0
DSS Export Volume Flow Curves= 0
DXF OffsetX= 0
DXF OffsetY= 0
DXF ScaleX= 1
DXF ScaleY= 10

--- Indian Creek 04.p01 (plan) ---

Plan Title=Multiple Run
Short Identifier=Multiple
Geom File=g01
Flow File=f01
Subcritical Flow
K Sum by GR= 0
Std Step Tol= 0.01
Critical Tol= 0.01
Num of Std Step Trials= 20
Max Error Tol= 0.3
Flow Tol Ratio= 0.001
Split Flow NTrial= 30
Split Flow Tol= 0.02
Split Flow Ratio= 0.02
Log Output Level= 0
Friction Slope Method= 1
Unsteady Friction Slope Method= 2
Unsteady Bridges Friction Slope Method= 1
Parabolic Critical Depth
Global Vel Dist=  1 , 1 , 1
Global Log Level= 0
CheckData=True
Encroach Param= -1, 0, 0, 0
BEGIN DESCRIPTION:
Multiple Run
END DESCRIPTION:

--- Indian Creek 04.f01 (steady flow) ---

Flow Title=Multiple
Number of Profiles=7
Profile Names=10-year,25-year,50-year,1pct_min,100-year,1pct_plu,500-year
River Rch & RM= Indian Creek 04,Reach-1,4627
     766    1276    1754    1169    2333    4655    4067
Boundary for River Rch & Prof#=Indian Creek 04,Reach-1,1
Up Type=0
Dn Type=3
Dn Slope=0.005
Boundary for River Rch & Prof#=Indian Creek 04,Reach-1,2
Up Type=0
Dn Type=3
Dn Slope=0.005
Boundary for River Rch & Prof#=Indian Creek 04,Reach-1,3
Up Type=0
Dn Type=3
Dn Slope=0.005
Boundary for River Rch & Prof#=Indian Creek 04,Reach-1,4
Up Type=0
Dn Type=3
Dn Slope=0.005
Boundary for River Rch & Prof#=Indian Creek 04,Reach-1,5
Up Type=0
Dn Type=3
Dn Slope=0.005
Boundary for River Rch & Prof#=Indian Creek 04,Reach-1,6
Up Type=0
Dn Type=3
Dn Slope=0.005
Boundary for River Rch & Prof#=Indian Creek 04,Reach-1,7
Up Type=0
Dn Type=3
Dn Slope=0.005

--- Indian Creek 04.g01 (geometry) ---

Geom Title=Existing Conditions
Program Version=4.10

River Reach=Indian Creek 04 ,Reach-1
Reach XY= 30
        1914125.       13892075.      1914219.13      13892077.1
      1914290.21     13892124.49      1914623.45     13892128.75
      1914751.82     13892201.29       1914914.9     13892414.61
       1915023.4     13892428.86      1915080.94     13892472.75
      1915214.49     13892473.79      1915293.27     13892425.21
      1915538.82     13892424.56        1915700.     13892475.41
      1915930.49     13892327.09       1916019.1     13892327.36
      1916075.01     13892367.41      1916159.64     13892325.29
       1916228.4     13892367.17      1916445.09     13892224.89
      1916584.67     13892273.63       1916714.5     13892273.81
      1916834.68     13892214.24      1916976.46     13892078.54
       1917264.5     13892073.78       1917675.1     13891932.33
      1917772.58     13892019.44      1917873.75     13892028.51
      1917917.32     13892068.48      1917927.07     13892219.14
      1918021.61     13892326.41        1918025.       13892425.

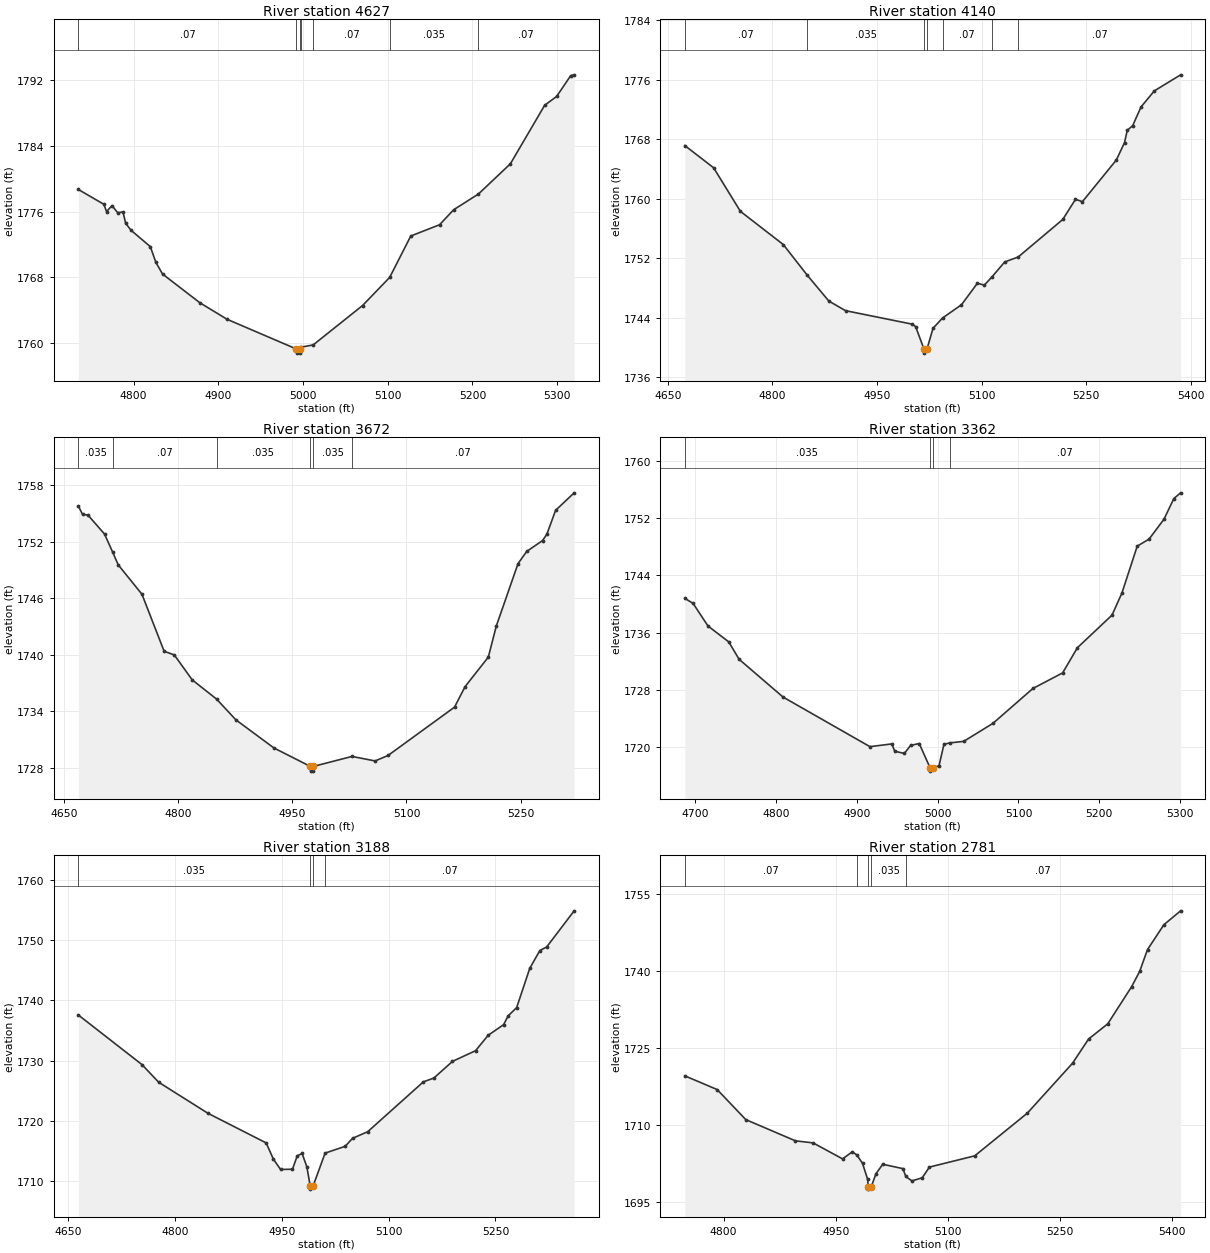
Type RM Length L Ch R = 1 ,4627    ,487,487,487
BEGIN DESCRIPTION:
Indian Creek 04 9.0
END DESCRIPTION:
XS GIS Cut Line= 3
      1914124.99     13892325.01        1914225.       13892075.
      1914125.03      13891775.1
#Sta/Elev= 30
  4734.7 1778.69  4764.8 1776.89    4768 1776.01  4774.5 1776.72  4781.2 1775.86
  4787.4 1775.96  4790.6 1774.57  4797.1 1773.71  4819.7 1771.74  4826.2 1769.84
  4834.1 1768.41  4878.1 1764.92  4910.2 1762.91  4992.2 1759.29  4992.4 1758.79
  4995.9 1758.79  4996.2 1759.29  4997.5 1759.51    5012 1759.79  5070.3 1764.58
  5102.3    1768  5127.2 1773.03  5161.2  1774.4  5177.8 1776.22  5207.1 1778.14
  5244.8 1781.81  5285.3 1788.93  5299.4    1790    5316 1792.53  5320.1 1792.63
#Mann= 7 ,-1 , 0
  4734.7     .07       0  4992.2    .035       0  4996.2     .07       0
  4997.5    .035       0    5012     .07       0  5102.3    .035       0
  5207.1     .07       0
Bank Sta=4992.2,4996.2
XS Rating Curve= 0 ,0
Exp/Cntr=0.3,0.1

Type RM Length L Ch R = 1 ,4140    ,468,468,468
BEGIN DESCRIPTION:
Indian Creek 04 8.0
END DESCRIPTION:
XS GIS Cut Line= 3
        1914425.       13892375.        1914675.       13892175.
      1914975.03     13891924.98
#Sta/Elev= 30
  4674.5 1767.15  4715.8 1764.16  4754.2  1758.3  4815.7 1753.83    4850 1749.71
    4881 1746.23  4904.9 1744.94  5000.8 1743.12  5005.4 1742.79  5017.5 1739.73
  5017.8 1739.23  5021.5 1739.73  5030.3 1742.57  5043.9 1743.95  5071.1 1745.74
  5093.9 1748.62  5103.9 1748.38  5114.4 1749.44    5133 1751.49  5152.4 1752.16
  5216.3 1757.21  5234.5 1759.92  5244.4  1759.6  5293.1 1765.21  5304.8 1767.55
  5308.7  1769.2  5316.5 1769.83  5328.5 1772.35  5347.5  1774.5  5385.2 1776.66
#Mann= 7 ,-1 , 0
  4674.5     .07       0    4850    .035       0  5017.5    .035       0
  5021.5    .035       0  5043.9     .07       0  5114.4    .035       0
  5152.4     .07       0
Bank Sta=5017.5,5021.5
XS Rating Curve= 0 ,0
Exp/Cntr=0.3,0.1

Type RM Length L Ch R = 1 ,3672    ,310,310,310
BEGIN DESCRIPTION:
Indian Creek 04 7.0
END DESCRIPTION:
XS GIS Cut Line= 3
        1914875.       13892725.        1915025.       13892425.
      1915124.99     13892125.03
#Sta/Elev= 30
  4668.8 1755.78  4674.3  1754.9  4681.4 1754.82  4703.2 1752.81  4713.8 1750.91
  4721.2 1749.54  4752.4 1746.42  4781.6 1740.36  4794.9 1739.98  4818.5 1737.33
  4850.4  1735.3  4875.9 1733.09  4925.8 1730.11  4973.7 1728.15    4974 1727.65
  4977.5 1727.65  4977.7 1728.15  5028.5 1729.21  5058.8 1728.73  5075.8 1729.31
  5163.2 1734.44    5177 1736.61  5207.6 1739.75  5218.1 1743.05  5246.6 1749.66
    5258 1750.96  5278.8 1752.11  5284.5 1752.78    5296 1755.32  5320.4 1757.18
#Mann= 6 ,-1 , 0
  4668.8    .035       0  4713.8     .07       0  4850.4    .035       0
  4973.7    .035       0  4977.7    .035       0  5028.5     .07       0
Bank Sta=4973.7,4977.7
XS Rating Curve= 0 ,0
Exp/Cntr=0.3,0.1

Type RM Length L Ch R = 1 ,3362    ,174,174,174
BEGIN DESCRIPTION:
Mapping XS 9dbcd8fc
END DESCRIPTION:
XS GIS Cut Line= 3
      1915218.67     13892720.02       1915310.9     13892473.44
      1915242.38     13892129.86
#Sta/Elev= 30
  4687.1 1740.81  4697.4 1740.09  4715.8 1736.94  4741.5 1734.72  4754.3 1732.29
  4808.7 1727.01  4916.2 1720.08  4943.3 1720.46  4946.9 1719.44  4958.8 1719.13
  4966.5 1720.25  4977.2 1720.52  4990.5 1717.16  4990.8 1716.66  4994.5 1717.16
  5001.7  1717.4  5007.8  1720.4  5014.7  1720.6  5032.3 1720.82  5068.5 1723.34
  5117.9 1728.21  5154.7 1730.39    5173 1733.91  5215.8 1738.46  5228.1 1741.56
    5247  1748.1  5261.7 1749.09  5280.1 1751.86  5292.3 1754.75  5300.7 1755.55
#Mann= 4 ,-1 , 0
  4687.1    .035       0  4990.5    .035       0  4994.5    .035       0
  5014.7     .07       0
Bank Sta=4990.5,4994.5
XS Rating Curve= 0 ,0
Exp/Cntr=0.3,0.1

Type RM Length L Ch R = 1 ,3188    ,407,407,407
BEGIN DESCRIPTION:
Indian Creek 04 6.0
END DESCRIPTION:
XS GIS Cut Line= 3
      1915325.01     13892724.99        1915475.       13892425.
      1915274.97     13892124.96
#Sta/Elev= 30
  4664.5 1737.57  4753.8 1729.35  4777.3 1726.42  4846.5 1721.27  4928.2 1716.36
  4938.3 1713.67  4948.4 1711.96  4965.1    1712  4971.8 1714.22  4978.6 1714.61
  4985.3 1712.39    4990  1709.2  4990.2  1708.7    4994  1709.2  5010.9 1714.67
  5039.1  1715.8  5049.4 1717.12  5070.7 1718.22  5148.9 1726.49  5163.5 1727.11
  5189.7 1729.88  5222.1 1731.65  5239.8 1734.21  5261.4 1735.96  5267.9 1737.43
  5279.8  1738.8  5298.2 1745.31  5312.3 1748.25    5322 1748.86  5360.5 1754.84
#Mann= 4 ,-1 , 0
  4664.5    .035       0    4990    .035       0    4994    .035       0
  5010.9     .07       0
Bank Sta=4990,4994
XS Rating Curve= 0 ,0
Exp/Cntr=0.3,0.1

Type RM Length L Ch R = 1 ,2781    ,448,448,448
BEGIN DESCRIPTION:
Indian Creek 04 5.0
END DESCRIPTION:
XS GIS Cut Line= 4
      1915724.98     13892625.04      1915843.32      13892427.8
      1915846.81     13892341.18      1915624.99     13892074.99
#Sta/Elev= 30
  4748.1 1719.54  4791.4 1716.87  4829.7 1711.02  4896.1 1706.89  4919.7 1706.49
  4959.1 1703.38  4972.2 1704.76  4978.2 1704.14  4985.8 1702.52  4992.5 1699.46
  4993.6 1697.99  4993.8 1697.49  4997.6 1697.99  5003.8 1700.49  5012.9 1702.33
  5039.9 1701.48  5043.7 1699.95  5051.9 1699.09  5065.7  1699.7  5075.3 1701.78
  5135.9 1703.97  5206.2 1712.27  5266.7 1721.99  5288.2 1726.71  5313.8 1729.66
  5345.7 1736.88  5356.5 1739.86    5367 1744.12    5389 1748.97  5411.3 1751.66
#Mann= 5 ,-1 , 0
  4748.1     .07       0  4978.2    .035       0  4993.6    .035       0
  4997.6    .035       0  5043.7     .07       0
Bank Sta=4993.6,4997.6
XS Rating Curve= 0 ,0
Exp/Cntr=0.3,0.1

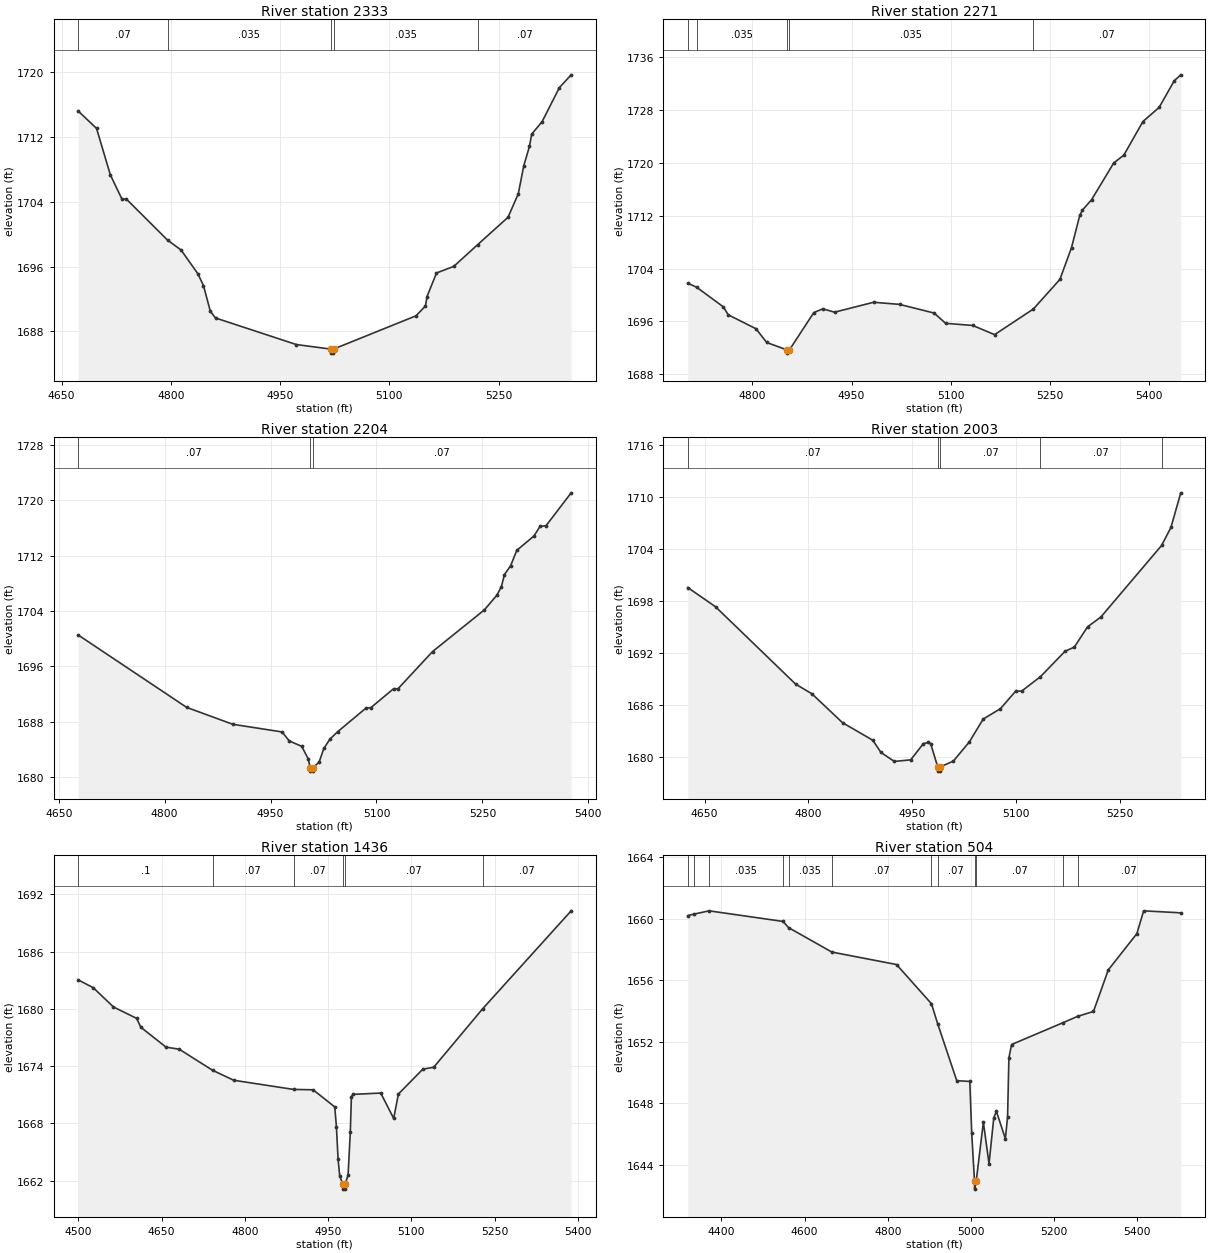
Type RM Length L Ch R = 1 ,2333    ,62,62,62
BEGIN DESCRIPTION:
Indian Creek 04 4.0
END DESCRIPTION:
XS GIS Cut Line= 3
        1916325.     13892674.99        1916225.       13892375.
      1916024.98     13892074.97
#Sta/Elev= 30
  4672.8 1715.22    4698 1713.07    4717 1707.32  4732.8 1704.35  4739.1 1704.33
  4795.5 1699.27    4814 1698.05  4837.1 1695.12  4844.8 1693.65  4854.3 1690.46
  4861.4 1689.65  4972.3 1686.37  5019.4 1685.81  5019.6 1685.31  5023.1 1685.31
  5023.4 1685.81  5136.6 1689.92  5149.6 1691.14  5151.7 1692.29  5164.7 1695.21
  5188.5 1696.03  5221.1  1698.7  5262.9 1702.09    5277 1704.99  5284.6 1708.48
  5292.3 1710.84  5295.4 1712.36  5309.8 1713.92  5333.4 1718.11  5349.6 1719.69
#Mann= 5 ,-1 , 0
  4672.8     .07       0  4795.5    .035       0  5019.4    .035       0
  5023.4    .035       0  5221.1     .07       0
Bank Sta=5019.4,5023.4
XS Rating Curve= 0 ,0
Exp/Cntr=0.3,0.1

Type RM Length L Ch R = 1 ,2271    ,67,67,67
BEGIN DESCRIPTION:
Indian Creek 04 4.1
END DESCRIPTION:
XS GIS Cut Line= 4
      1916402.72     13892593.72      1916320.26     13892389.74
      1916150.99     13892211.79      1916020.77     13891964.38
#Sta/Elev= 30
  4702.5  1701.8  4716.1 1701.17  4756.3 1698.21  4763.6 1697.01  4805.6  1694.9
  4821.8 1692.82  4852.2 1691.71  4852.4 1691.21  4856.2 1691.71    4893 1697.35
  4906.5 1697.91  4924.4 1697.41  4983.4 1698.91  5022.6 1698.59  5074.8 1697.28
  5092.3 1695.72  5133.2  1695.4  5166.3 1694.01  5224.9 1697.89    5265 1702.37
  5282.6  1707.2    5295 1712.05  5298.9 1712.85  5312.8 1714.42  5346.3 1719.99
  5361.7 1721.19  5390.5 1726.27    5415 1728.41  5437.9 1732.45  5447.7 1733.34
#Mann= 5 ,-1 , 0
  4702.5     .07       0  4716.1    .035       0  4852.2    .035       0
  4856.2    .035       0  5224.9     .07       0
Bank Sta=4852.2,4856.2
XS Rating Curve= 0 ,0
Exp/Cntr=0.3,0.1

Type RM Length L Ch R = 1 ,2204    ,201,201,201
BEGIN DESCRIPTION:
Mapping XS c400ca64
END DESCRIPTION:
XS GIS Cut Line= 3
      1916446.83      13892578.9      1916374.96     13892386.09
       1916122.2     13891963.59
#Sta/Elev= 30
  4677.6 1700.52  4831.1 1690.05  4896.4  1687.6  4966.3 1686.49  4976.6 1685.18
  4994.1 1684.41  5003.4 1682.59  5006.1 1681.32  5006.3 1680.82  5009.8 1680.82
  5010.1 1681.32  5018.8 1682.13  5025.5 1684.11  5034.1 1685.45    5045 1686.52
    5085 1689.93    5092    1690  5124.3 1692.75  5130.3 1692.72  5179.4 1698.12
  5252.8 1704.15  5270.4 1706.26  5276.9 1707.51  5281.2 1709.26    5290 1710.55
  5298.7 1712.77    5323 1714.84  5331.5 1716.22  5340.2 1716.34  5375.7 1721.09
#Mann= 3 ,-1 , 0
  4677.6     .07       0  5006.1     .05       0  5010.1     .07       0
Bank Sta=5006.1,5010.1
XS Rating Curve= 0 ,0
Exp/Cntr=0.3,0.1

Type RM Length L Ch R = 1 ,2003    ,567,567,567
BEGIN DESCRIPTION:
Indian Creek 04 3.0
END DESCRIPTION:
XS GIS Cut Line= 4
      1916474.99     13892575.02      1916551.31     13892346.06
      1916476.55     13892176.55      1916275.03     13891975.03
#Sta/Elev= 30
  4625.8 1699.56  4665.8 1697.35  4781.6 1688.42  4804.9 1687.32  4849.2 1683.98
  4892.9 1681.96  4904.4 1680.57  4923.9 1679.52  4947.6  1679.7  4965.8 1681.57
  4973.1 1681.71  4976.4 1681.57  4986.5  1678.9  4986.8  1678.4  4990.3  1678.4
  4990.5  1678.9  5009.2 1679.56  5032.2 1681.77  5052.2  1684.4  5077.1  1685.6
  5098.9  1687.6    5108 1687.64  5134.9 1689.29  5170.4 1692.22  5183.8  1692.7
  5202.8 1695.03  5221.9 1696.15  5309.7 1704.41  5323.2 1706.49  5337.4 1710.48
#Mann= 5 ,-1 , 0
  4625.8     .07       0  4986.5     .05       0  4990.5     .07       0
  5134.9     .07       0  5309.7    .035       0
Bank Sta=4986.5,4990.5
XS Rating Curve= 0 ,0
Exp/Cntr=0.3,0.1

Type RM Length L Ch R = 1 ,1436    ,932,932,932
BEGIN DESCRIPTION:
Indian Creek 04 2.0
END DESCRIPTION:
XS GIS Cut Line= 4
      1916873.94     13892556.09      1916981.76     13892317.32
        1916975.       13892075.      1916705.98     13891801.12
#Sta/Elev= 30
  4499.8 1683.03  4527.2  1682.2  4563.4 1680.19  4605.1    1679  4612.7 1678.07
    4658 1675.99  4681.9 1675.77  4742.1 1673.56    4780 1672.52  4887.9 1671.56
  4923.1 1671.52  4962.1 1669.73  4965.1 1667.67  4968.1 1664.25  4971.1 1662.48
  4976.7 1661.62  4976.9 1661.12  4980.4 1661.12  4980.7 1661.62  4986.1 1662.58
  4990.2 1667.15  4992.1  1670.8  4995.1 1671.04    5045 1671.18  5068.3 1668.52
  5076.8 1671.08  5120.8 1673.68  5140.4 1673.88  5228.4 1679.99  5388.1 1690.26
#Mann= 6 ,-1 , 0
  4499.8      .1       0  4742.1     .07       0  4887.9     .07       0
  4976.7     .05       0  4980.7     .07       0  5228.4     .07       0
Bank Sta=4976.7,4980.7
XS Rating Curve= 0 ,0
Exp/Cntr=0.3,0.1

Type RM Length L Ch R = 1 ,504     ,0,0,0
BEGIN DESCRIPTION:
Indian Creek 04 1.0
END DESCRIPTION:
XS GIS Cut Line= 3
      1917430.31      13892579.7        1917825.       13892025.
      1917638.22     13891556.12
#Sta/Elev= 30
  4319.2  1660.2  4334.7  1660.3  4370.4 1660.51  4548.4 1659.82  4561.4 1659.42
  4665.6 1657.83  4821.1 1657.02  4905.2 1654.47    4920 1653.18    4966 1649.47
  4997.4 1649.42    5002 1646.04  5008.7 1642.92  5008.9 1642.42  5012.7 1642.92
    5030 1646.77  5043.6 1644.07  5055.1 1647.07  5061.4 1647.47  5082.9  1645.7
  5088.2  1647.1  5091.4 1650.95  5097.9 1651.82  5222.5 1653.25  5256.7 1653.65
  5294.8 1653.97  5330.4 1656.67  5399.2 1659.03  5415.4 1660.51  5504.7 1660.38
#Mann= 12 ,-1 , 0
  4319.2    .035       0  4334.7     .07       0  4370.4    .035       0
  4548.4     .07       0  4561.4    .035       0  4665.6     .07       0
  4905.2      .1       0    4920     .07       0  5008.7     .05       0
  5012.7     .07       0  5222.5      .1       0  5256.7     .07       0
Bank Sta=5008.7,5012.7
XS Rating Curve= 0 ,0
Exp/Cntr=0.3,0.1

Chan Stop Cuts=-1
Use User Specified Reach Order=0
Composite Channel Slope=5