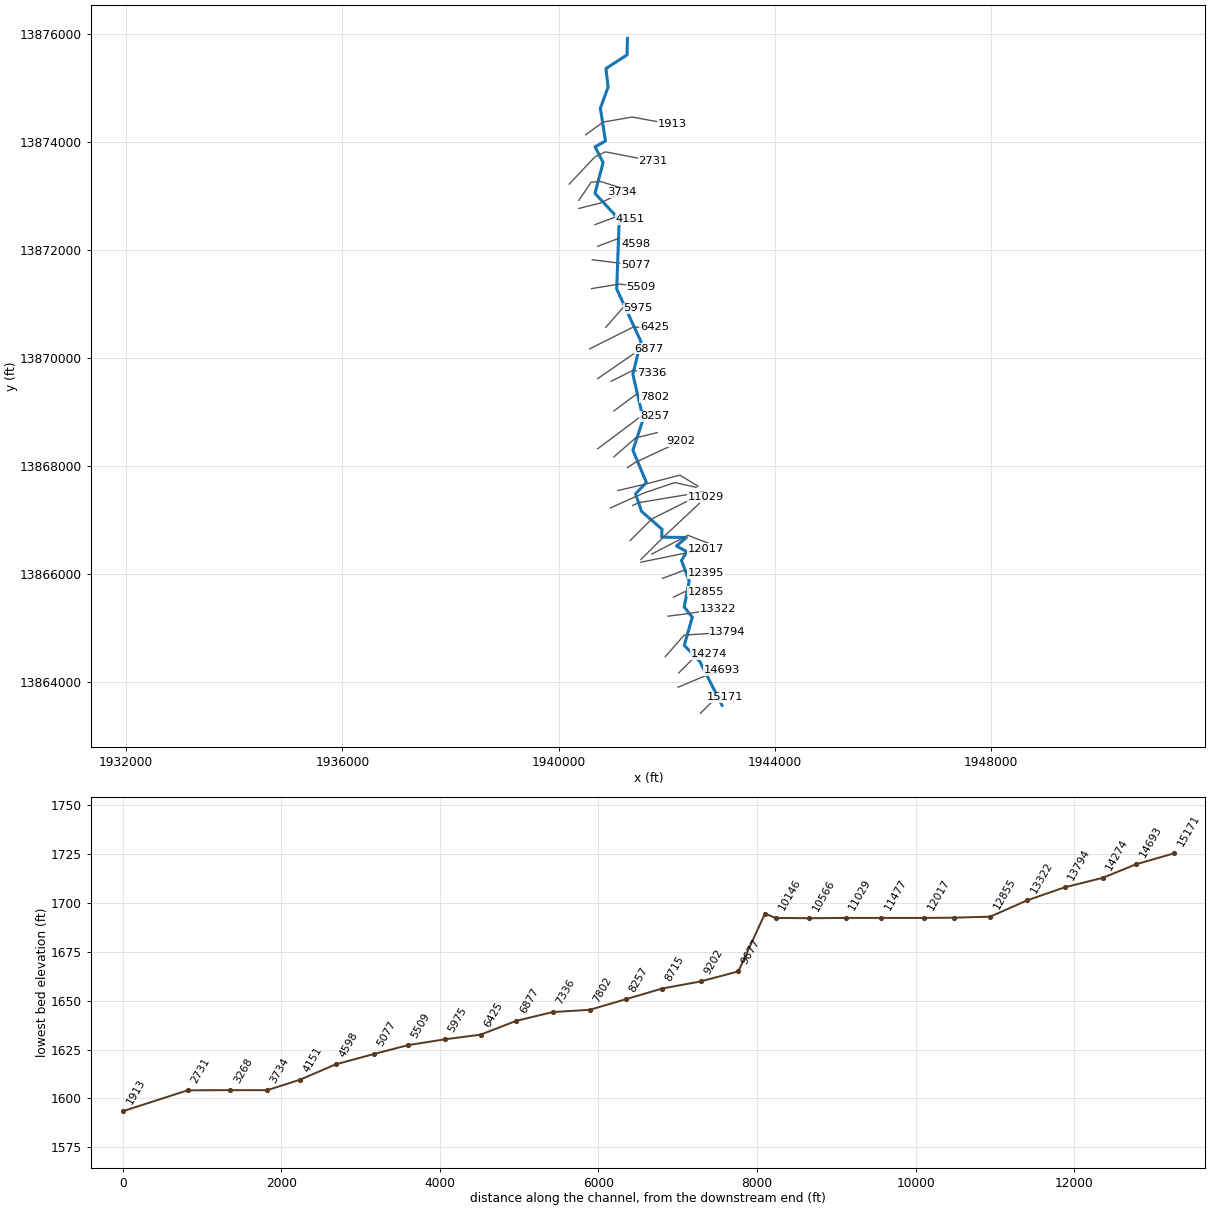
--- Klein Hollow.prj (project) ---

Proj Title=Klein Hollow Base Level Engineering
Current Plan=p01
Default Exp/Contr=0.3,0.1
English Units
Geom File=g01
Flow File=f01
Plan File=p01
Y Axis Title=Elevation
X Axis Title(PF)=Main Channel Distance
X Axis Title(XS)=Station
BEGIN DESCRIPTION:
Klein Hollow
END DESCRIPTION:
DSS Export Rating Curves= 0
DSS Export Rating Curve Sorted= 0
DSS Export Volume Flow Curves= 0
DXF OffsetX= 0
DXF OffsetY= 0
DXF ScaleX= 1
DXF ScaleY= 10

--- Klein Hollow.p01 (plan) ---

Plan Title=Multiple Run
Short Identifier=Multiple
Geom File=g01
Flow File=f01
Subcritical Flow
K Sum by GR= 0
Std Step Tol= 0.01
Critical Tol= 0.01
Num of Std Step Trials= 20
Max Error Tol= 0.3
Flow Tol Ratio= 0.001
Split Flow NTrial= 30
Split Flow Tol= 0.02
Split Flow Ratio= 0.02
Log Output Level= 0
Friction Slope Method= 1
Unsteady Friction Slope Method= 2
Unsteady Bridges Friction Slope Method= 1
Parabolic Critical Depth
Global Vel Dist=  1 , 1 , 1
Global Log Level= 0
CheckData=True
Encroach Param= -1, 0, 0, 0
BEGIN DESCRIPTION:
Multiple Run
END DESCRIPTION:

--- Klein Hollow.f01 (steady flow) ---

Flow Title=Multiple
Program Version=4.10
Number of Profiles= 7
Profile Names=10-year,25-year,50-year,1pct_min,100-year,1pct_plu,500-year
River Rch & RM=Klein Hollow,Reach-1         ,15171
    1944    3420    4872    3355    6694   13356   12471
River Rch & RM=Klein Hollow,Reach-1         ,13322
    2582    4582    6563    4535    9049   18054   16990
River Rch & RM=Klein Hollow,Reach-1         ,6425
    3329    5965    8598    5971   11914   23772   22606
Boundary for River Rch & Prof#=Klein Hollow,Reach-1         , 1
Up Type= 0
Dn Type= 3
Dn Slope=0.008
Boundary for River Rch & Prof#=Klein Hollow,Reach-1         , 2
Up Type= 0
Dn Type= 3
Dn Slope=0.008
Boundary for River Rch & Prof#=Klein Hollow,Reach-1         , 3
Up Type= 0
Dn Type= 3
Dn Slope=0.008
Boundary for River Rch & Prof#=Klein Hollow,Reach-1         , 4
Up Type= 0
Dn Type= 3
Dn Slope=0.008
Boundary for River Rch & Prof#=Klein Hollow,Reach-1         , 5
Up Type= 0
Dn Type= 3
Dn Slope=0.008
Boundary for River Rch & Prof#=Klein Hollow,Reach-1         , 6
Up Type= 0
Dn Type= 3
Dn Slope=0.008
Boundary for River Rch & Prof#=Klein Hollow,Reach-1         , 7
Up Type= 0
Dn Type= 3
Dn Slope=0.008
DSS Import GetInterval= 0
DSS Import GetPeak= 0
DSS Import FillOption= 0

--- Klein Hollow.g01 (geometry) ---

Geom Title=Existing Conditions
Program Version=4.10

River Reach=Klein Hollow    ,Reach-1
Reach XY= 30
        1943025.       13863575.      1942616.86     13864381.06
      1942326.05     13864685.43      1942475.21     13865204.95
      1942324.96     13865394.98       1942417.5       13865875.
      1942274.61     13866254.87      1942373.51     13866419.15
      1942181.97     13866524.77      1942366.48     13866681.71
      1941911.19     13866688.22      1941913.89     13866835.05
      1941535.76     13867165.32      1941425.01     13867490.48
       1941625.5     13867699.96      1941374.77     13868299.92
      1941567.44       13868875.      1941374.61     13869704.87
      1941524.61     13870309.84      1941075.77     13871285.69
      1941122.77     13872569.07      1940674.33     13873054.92
        1940825.       13873625.      1940675.86     13873914.69
      1940868.01     13874024.76      1940774.19     13874630.03
      1940917.67      13875024.9      1940876.05     13875364.57
      1941267.19     13875618.79        1941275.       13875925.

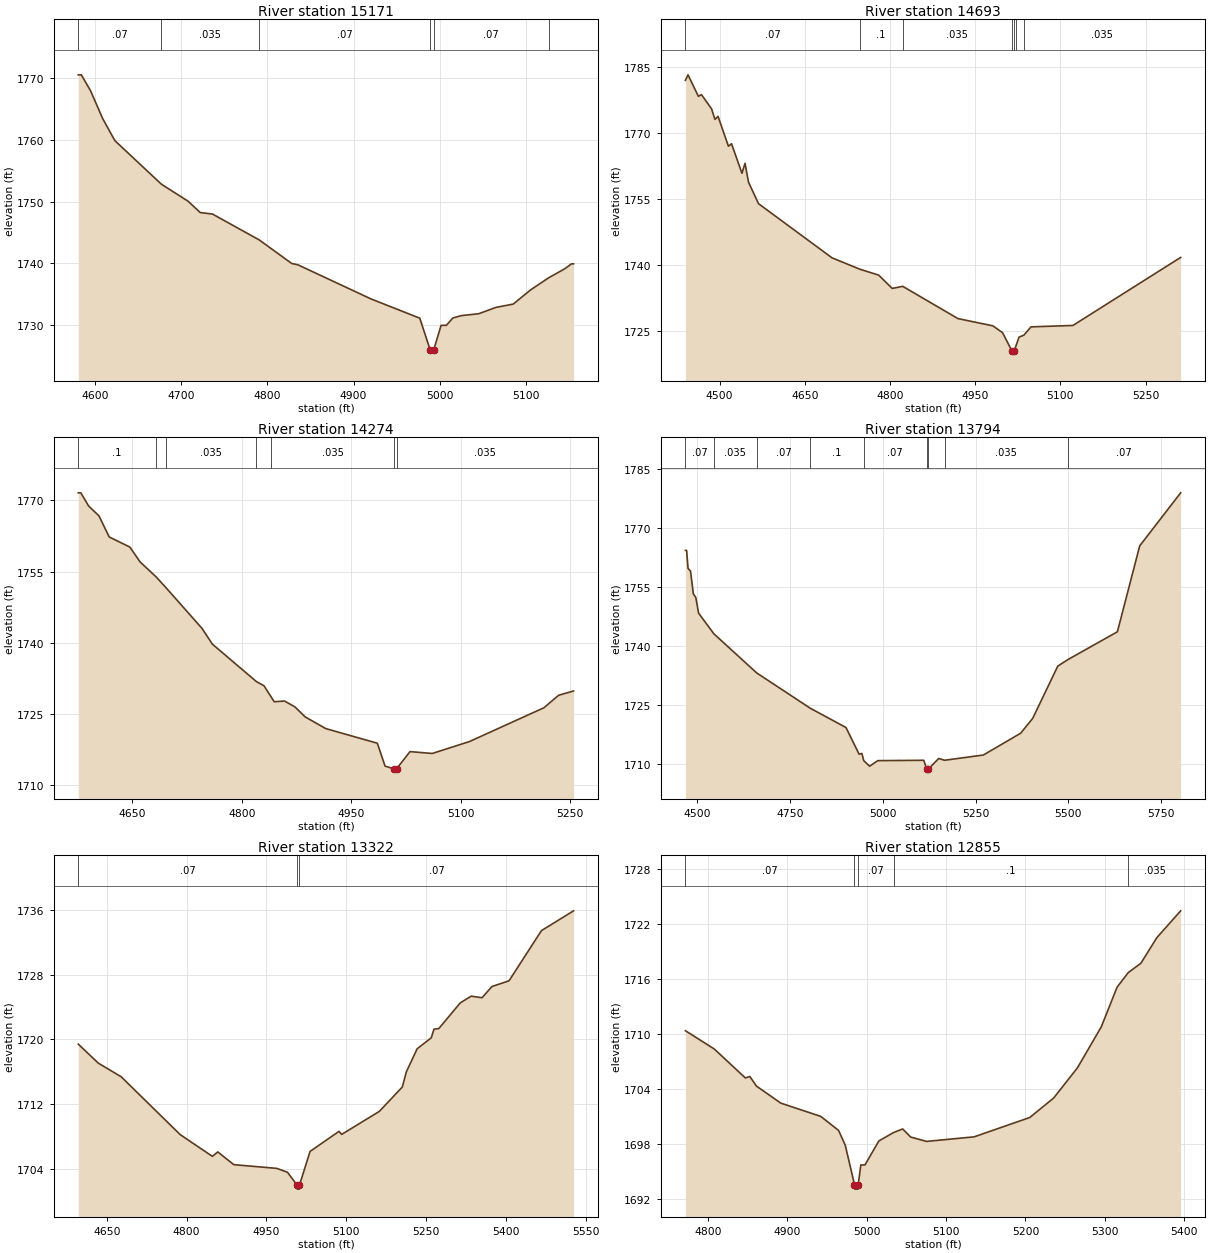
Type RM Length L Ch R = 1 ,15171   ,478,478,478
BEGIN DESCRIPTION:
Klein Hollow 30.0
END DESCRIPTION:
XS GIS Cut Line= 3
      1942624.99     13863424.99        1942925.       13863725.
      1943075.03       13863725.
#Sta/Elev= 30
  4580.8 1770.53  4584.3 1770.53    4595 1767.95  4609.1 1763.43  4623.2 1759.87
  4677.1 1752.82  4708.1 1750.06  4722.2 1748.22  4736.4 1747.98  4790.7 1743.78
  4828.3 1739.97  4835.4 1739.76  4920.2 1734.23  4976.8 1731.11  4988.9 1725.95
  4989.2 1725.45  4992.7 1725.45  4992.9 1725.95  5001.5 1729.95  5007.6 1729.95
  5015.1 1731.14  5025.1 1731.53  5045.1 1731.83  5065.1 1732.86  5085.1 1733.39
  5105.1 1735.67  5126.3 1737.66  5145.1 1739.13  5152.6 1739.91  5155.1 1739.91
#Mann= 6 ,-1 , 0
  4580.8     .07       0  4677.1    .035       0  4790.7     .07       0
  4988.9     .05       0  4992.9     .07       0  5126.3    .035       0
Bank Sta=4988.9,4992.9
XS Rating Curve= 0 ,0
Exp/Cntr=0.3,0.1

Type RM Length L Ch R = 1 ,14693   ,419,419,419
BEGIN DESCRIPTION:
Klein Hollow 29.0
END DESCRIPTION:
XS GIS Cut Line= 3
      1942212.52     13863909.62        1942725.       13864125.
      1943024.97     13864224.99
#Sta/Elev= 30
  4439.8 1781.98  4444.4 1783.24  4462.7 1778.34  4468.1 1778.73  4485.9 1775.49
  4491.9 1773.09  4497.3 1773.78  4515.6 1766.98    4521 1767.55  4539.4 1760.82
  4544.8 1763.09    4551 1758.78  4568.5 1753.91  4698.1 1741.56  4746.8 1738.99
  4780.2 1737.63    4804  1734.6  4822.5 1735.08  4919.8 1727.73  4981.1 1726.09
  4998.3 1724.53  5014.8 1720.37    5015 1719.87  5018.8 1720.37  5021.4 1721.33
  5027.3 1723.51  5035.8 1723.96  5048.4 1725.85  5122.2 1726.17  5311.9 1741.66
#Mann= 7 ,-1 , 0
  4439.8     .07       0  4746.8      .1       0  4822.5    .035       0
  5014.8    .035       0  5018.8    .035       0  5021.4     .07       0
  5035.8    .035       0
Bank Sta=5014.8,5018.8
XS Rating Curve= 0 ,0
Exp/Cntr=0.3,0.1

Type RM Length L Ch R = 1 ,14274   ,480,480,480
BEGIN DESCRIPTION:
Klein Hollow 28.0
END DESCRIPTION:
XS GIS Cut Line= 3
        1942225.       13864175.        1942525.       13864475.
      1942774.99       13864525.
#Sta/Elev= 30
  4575.7 1771.58  4579.2 1771.58  4589.8 1768.81    4604 1766.74  4618.1 1762.28
  4646.4 1760.15  4660.5 1757.01  4682.5 1753.86  4695.7 1751.64  4745.4 1743.01
  4759.5 1739.71    4820  1731.8  4830.3 1730.94  4840.4 1728.52  4844.4 1727.56
  4858.5 1727.71  4872.7 1726.49  4886.8 1724.37  4915.1  1721.9  4985.8 1718.82
  4996.4    1714  5008.2 1713.44  5008.4 1712.94  5012.2 1713.44  5030.6 1717.05
  5061.1 1716.66  5112.1 1719.17  5214.1 1726.28  5234.5 1728.93  5254.9 1729.83
#Mann= 7 ,-1 , 0
  4575.7      .1       0  4682.5     .07       0  4695.7    .035       0
    4820     .07       0  4840.4    .035       0  5008.2    .035       0
  5012.2    .035       0
Bank Sta=5008.2,5012.2
XS Rating Curve= 0 ,0
Exp/Cntr=0.3,0.1

Type RM Length L Ch R = 1 ,13794   ,472,472,472
BEGIN DESCRIPTION:
Klein Hollow 27.0
END DESCRIPTION:
XS GIS Cut Line= 3
      1941974.98     13864474.98        1942325.       13864875.
      1943125.01       13864925.
#Sta/Elev= 30
  4469.1 1764.27  4472.4 1764.27  4476.2  1759.7  4482.9 1758.98  4490.5 1753.19
  4497.1 1752.27  4504.7 1748.28  4545.8 1743.03    4661 1733.08  4805.4 1724.08
  4901.4 1719.18  4936.6  1712.4  4944.2 1712.58  4949.2 1710.74    4965 1709.33
  4986.9 1710.75  5110.8 1710.84  5118.7 1708.58    5119 1708.08    5123 1708.58
  5150.9  1711.3  5166.9 1710.85  5271.2 1712.18  5371.4 1717.72  5403.9  1721.5
  5471.5 1734.81  5498.2 1736.44  5631.9 1743.55    5692 1765.42  5802.2 1778.92
#Mann= 9 ,-1 , 0
  4469.1     .07       0  4545.8    .035       0    4661     .07       0
  4805.4      .1       0  4949.2     .07       0  5118.7     .05       0
    5123     .07       0  5166.9    .035       0  5498.2     .07       0
Bank Sta=5118.7,5123
XS Rating Curve= 0 ,0
Exp/Cntr=0.3,0.1

Type RM Length L Ch R = 1 ,13322   ,467,467,467
BEGIN DESCRIPTION:
Klein Hollow 26.0
END DESCRIPTION:
XS GIS Cut Line= 3
      1942025.03       13865225.        1942425.       13865275.
      1942944.43     13865365.87
#Sta/Elev= 30
  4596.6 1719.41  4634.4 1717.05  4677.2 1715.37  4788.1  1708.2  4848.5 1705.51
  4858.6 1706.06  4888.8 1704.48  4969.5 1704.02  4989.6 1703.54  5007.5 1701.95
  5007.9 1701.45  5011.8 1701.45  5012.1 1701.95    5032 1706.12  5086.4 1708.61
  5091.4 1708.23  5162.1 1711.08  5205.3  1714.1  5212.9 1715.98  5233.2 1718.84
  5259.7  1720.2  5264.8 1721.27  5273.8 1721.34  5314.1 1724.52  5334.7 1725.36
    5355 1725.16  5373.6 1726.55  5405.8 1727.26  5466.7 1733.48    5527 1735.93
#Mann= 3 ,-1 , 0
  4596.6     .07       0  5007.5     .05       0  5012.1     .07       0
Bank Sta=5007.5,5012.1
XS Rating Curve= 0 ,0
Exp/Cntr=0.3,0.1

Type RM Length L Ch R = 1 ,12855   ,460,460,460
BEGIN DESCRIPTION:
Klein Hollow 25.0
END DESCRIPTION:
XS GIS Cut Line= 3
      1942124.97     13865574.98        1942325.       13865675.
      1942724.95       13865675.
#Sta/Elev= 30
  4771.9 1710.37  4808.3 1708.37  4847.4 1705.21    4853 1705.37  4861.4 1704.32
  4892.1 1702.46  4942.4 1701.01  4964.8 1699.48  4973.2 1697.86  4984.8 1693.57
  4985.2 1693.07  4989.2 1693.07  4989.5 1693.57  4992.8 1695.71    4998 1695.71
  5015.5 1698.33    5034 1699.25  5045.5 1699.64  5055.5 1698.76  5075.5 1698.28
  5135.5 1698.78  5205.5 1700.89  5235.5 1703.01  5265.5 1706.31  5295.5 1710.78
  5315.5 1715.13  5329.6 1716.72  5345.5 1717.74  5365.5 1720.53  5395.5 1723.46
#Mann= 5 ,-1 , 0
  4771.9     .07       0  4984.8     .05       0  4989.5     .07       0
    5034      .1       0  5329.6    .035       0
Bank Sta=4984.8,4989.5
XS Rating Curve= 0 ,0
Exp/Cntr=0.3,0.1

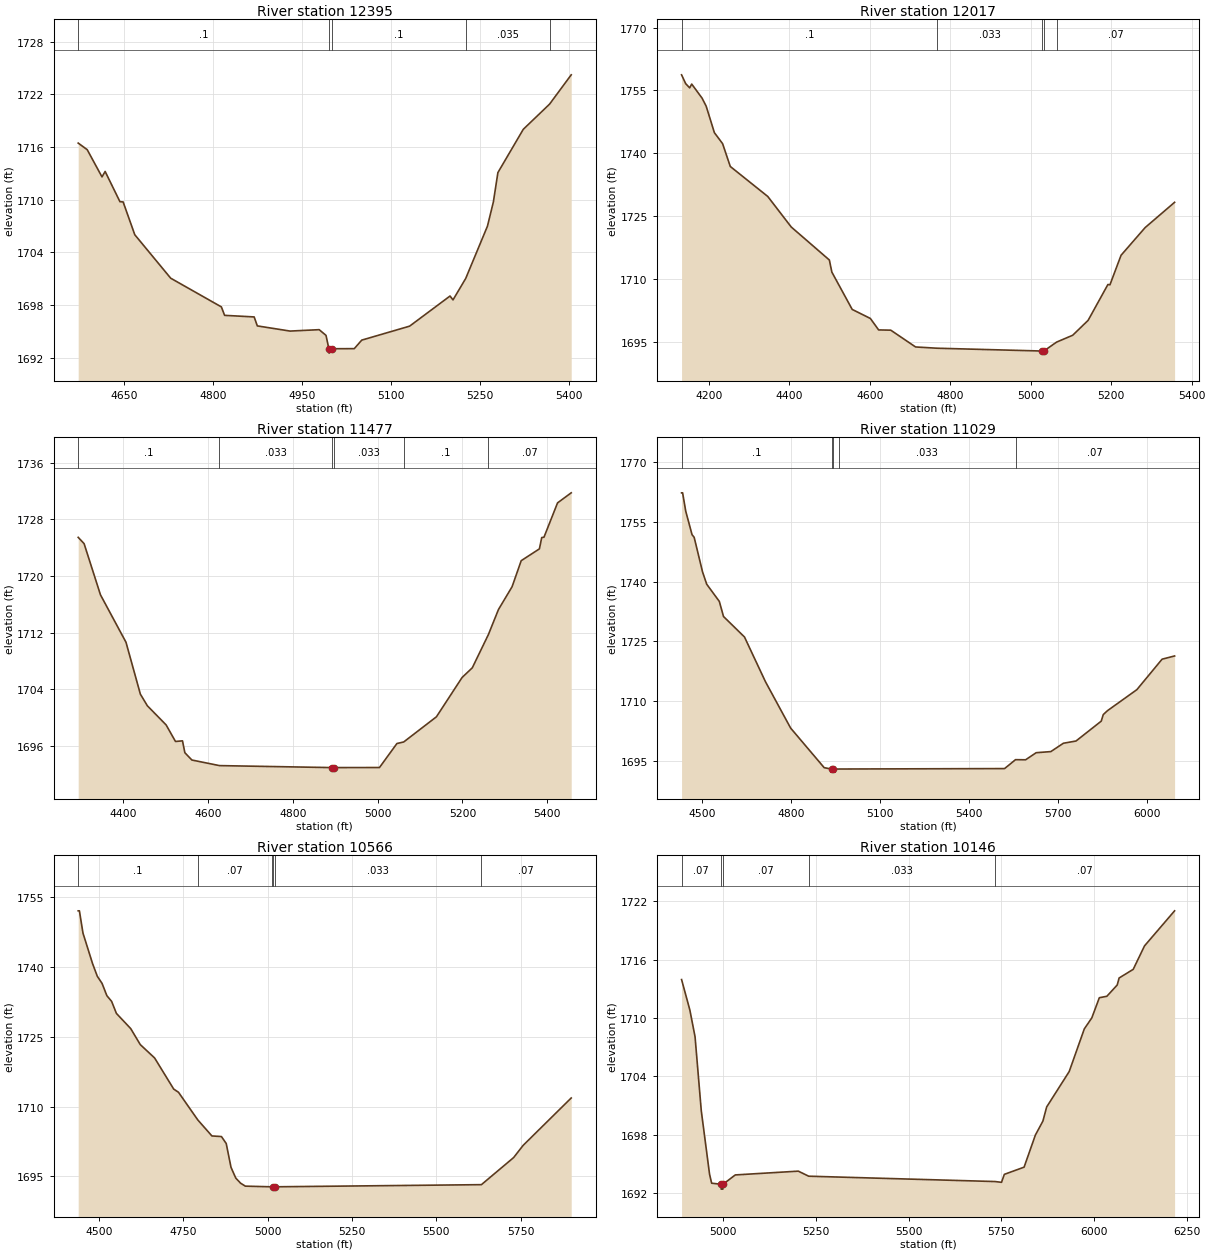
Type RM Length L Ch R = 1 ,12395   ,378,378,378
BEGIN DESCRIPTION:
Klein Hollow 24.0
END DESCRIPTION:
XS GIS Cut Line= 3
      1941924.96     13865924.99        1942325.       13866075.
      1942725.05     13866024.99
#Sta/Elev= 30
  4573.1 1716.45  4588.3  1715.7  4613.2  1712.6  4618.5 1713.22  4643.4 1709.78
  4648.8 1709.75  4668.4 1706.02  4728.9 1701.07  4814.3  1697.8  4819.7 1696.84
  4869.5 1696.66  4874.8 1695.64    4930 1695.05    4979 1695.21  4990.5 1694.56
  4995.3 1693.04  4995.7 1692.54    5000 1693.04  5038.1 1693.05  5050.7 1694.02
  5131.3 1695.61  5199.4 1699.04  5204.4  1698.6  5225.8 1701.04  5262.4 1706.99
  5272.4 1709.75    5280 1713.09  5322.8 1718.02    5367 1720.88  5403.5 1724.22
#Mann= 5 ,-1 , 0
  4573.1      .1       0  4995.3     .05       0    5000      .1       0
  5225.8    .035       0    5367     .07       0
Bank Sta=4995.3,5000
XS Rating Curve= 0 ,0
Exp/Cntr=0.3,0.1

Type RM Length L Ch R = 1 ,12017   ,540,540,540
BEGIN DESCRIPTION:
Klein Hollow 23.0
END DESCRIPTION:
XS GIS Cut Line= 3
      1941525.04     13866225.01      1942415.87     13866406.92
      1942724.95     13866474.99
#Sta/Elev= 30
  4131.9 1758.73  4142.1 1756.63    4152 1755.62  4157.1 1756.53  4182.9 1753.17
  4193.1 1751.25  4213.5 1744.94  4233.9 1742.33    4253 1736.89  4346.2 1729.74
  4404.5 1722.47  4499.3  1714.6  4505.5 1711.72  4556.1 1702.82  4601.3 1700.67
  4621.8 1697.94    4652 1697.88  4713.6 1693.88    4767 1693.58  5027.6 1692.91
    5028 1692.41  5032.5 1692.91  5064.3 1695.04  5104.3 1696.67  5142.6 1700.22
  5191.8 1708.76  5196.9  1708.7  5224.5 1715.73  5284.4 1722.33  5357.6 1728.35
#Mann= 5 ,-1 , 0
  4131.9      .1       0    4767    .033       0  5027.6    .033       0
  5032.5    .033       0  5064.3     .07       0
Bank Sta=5027.6,5032.5
XS Rating Curve= 0 ,0
Exp/Cntr=0.3,0.1

Type RM Length L Ch R = 1 ,11477   ,448,448,448
BEGIN DESCRIPTION:
Klein Hollow 22.0
END DESCRIPTION:
XS GIS Cut Line= 3
      1941725.01       13866375.      1942393.54     13866722.32
      1942775.01       13866575.
#Sta/Elev= 30
  4294.2 1725.45  4308.1 1724.56  4346.7 1717.33  4406.9 1710.62  4440.8 1703.29
  4457.2 1701.65  4501.5 1698.94  4523.6  1696.6  4540.1 1696.69  4545.7 1695.01
  4562.2 1693.98  4627.2 1693.19  4891.4 1692.91  4891.8 1692.41  4896.3 1692.91
  5004.5 1692.92  5045.6 1696.31  5061.6 1696.53  5138.8 1700.09  5199.2 1705.64
  5223.3 1707.01  5261.2  1711.7    5285 1715.25  5317.1 1718.47  5338.6 1722.15
  5381.5 1723.82    5387 1725.42  5392.3 1725.47  5424.3 1730.32  5456.5 1731.74
#Mann= 6 ,-1 , 0
  4294.2      .1       0  4627.2    .033       0  4891.4    .033       0
  4896.3    .033       0  5061.6      .1       0  5261.2     .07       0
Bank Sta=4891.4,4896.3
XS Rating Curve= 0 ,0
Exp/Cntr=0.3,0.1

Type RM Length L Ch R = 1 ,11029   ,463,463,463
BEGIN DESCRIPTION:
Klein Hollow 21.0
END DESCRIPTION:
XS GIS Cut Line= 3
      1941525.02     13866275.02        1941925.       13866675.
      1942724.97     13867424.97
#Sta/Elev= 30
  4430.2 1762.37  4433.7 1762.37  4444.3 1757.73  4465.5 1751.85  4472.6  1751.2
  4500.9 1742.49    4515 1739.39  4557.5 1735.07  4571.6 1731.28  4642.3 1726.13
    4713 1714.89  4797.9 1703.23    4911 1693.28  4936.7 1692.91  4937.1 1692.41
  4941.8 1692.91  4961.9 1692.94  5519.2 1693.05  5556.1 1695.29  5590.1 1695.26
  5625.7 1697.04  5675.1 1697.32  5717.5 1699.42    5760 1699.98    5845 1704.97
  5851.9 1706.62    5866  1707.6  5965.2 1712.89  6050.2 1720.55  6092.4 1721.36
#Mann= 5 ,-1 , 0
  4430.2      .1       0  4936.7    .033       0  4941.8      .1       0
  4961.9    .033       0  5556.1     .07       0
Bank Sta=4936.7,4941.8
XS Rating Curve= 0 ,0
Exp/Cntr=0.3,0.1

Type RM Length L Ch R = 1 ,10566   ,420,420,420
BEGIN DESCRIPTION:
Klein Hollow 20.0
END DESCRIPTION:
XS GIS Cut Line= 3
      1941324.98     13866624.98        1941725.       13867025.
      1942524.97     13867424.98
#Sta/Elev= 30
  4439.1 1752.13  4442.7 1752.13  4453.3 1747.33  4481.6 1740.79  4495.7 1738.05
  4509.8 1736.52    4524 1733.88  4538.1 1732.65  4552.3 1730.06  4594.7 1726.79
    4623 1723.35  4665.4 1720.48    4722 1713.78  4736.1  1713.1  4793.3 1707.15
  4835.1  1703.7  4863.4 1703.57  4877.5 1702.07  4891.7 1696.95  4905.8 1694.64
    4920 1693.54  4934.1  1692.9    5012 1692.76  5016.1 1692.76  5016.6 1692.26
  5021.4 1692.76  5633.2 1693.22  5728.7 1699.05  5756.7 1701.66  5899.2 1711.87
#Mann= 6 ,-1 , 0
  4439.1      .1       0  4793.3     .07       0    5012    .033       0
  5016.1     .05       0  5021.4    .033       0  5633.2     .07       0
Bank Sta=5016.1,5021.4
XS Rating Curve= 0 ,0
Exp/Cntr=0.3,0.1

Type RM Length L Ch R = 1 ,10146   ,132,132,132
BEGIN DESCRIPTION:
Klein Hollow 19.0
END DESCRIPTION:
XS GIS Cut Line= 3
      1941375.04     13867275.02        1941475.       13867325.
      1942674.99       13867525.
#Sta/Elev= 30
  4888.6 1713.97  4910.9 1710.84  4924.9 1708.09  4941.7 1700.47    4964 1693.94
  4969.6 1693.02  4994.9 1692.91  4995.3 1692.41  4999.8 1692.41  5000.2 1692.91
  5033.3 1693.87  5203.1 1694.26    5231 1693.74  5733.1 1693.19  5750.6 1693.11
  5758.2 1693.93  5811.4 1694.67  5841.8 1697.97  5862.1 1699.41  5872.2 1700.86
    5933 1704.51  5973.6 1708.89  5993.9 1710.03  6014.1  1712.1  6034.4 1712.25
  6062.3 1713.41  6067.4 1714.13  6105.4 1715.02  6135.8 1717.43  6216.9 1721.04
#Mann= 5 ,-1 , 0
  4888.6     .07       0  4994.9     .05       0  5000.2     .07       0
    5231    .033       0  5733.1     .07       0
Bank Sta=4994.9,5000.2
XS Rating Curve= 0 ,0
Exp/Cntr=0.3,0.1

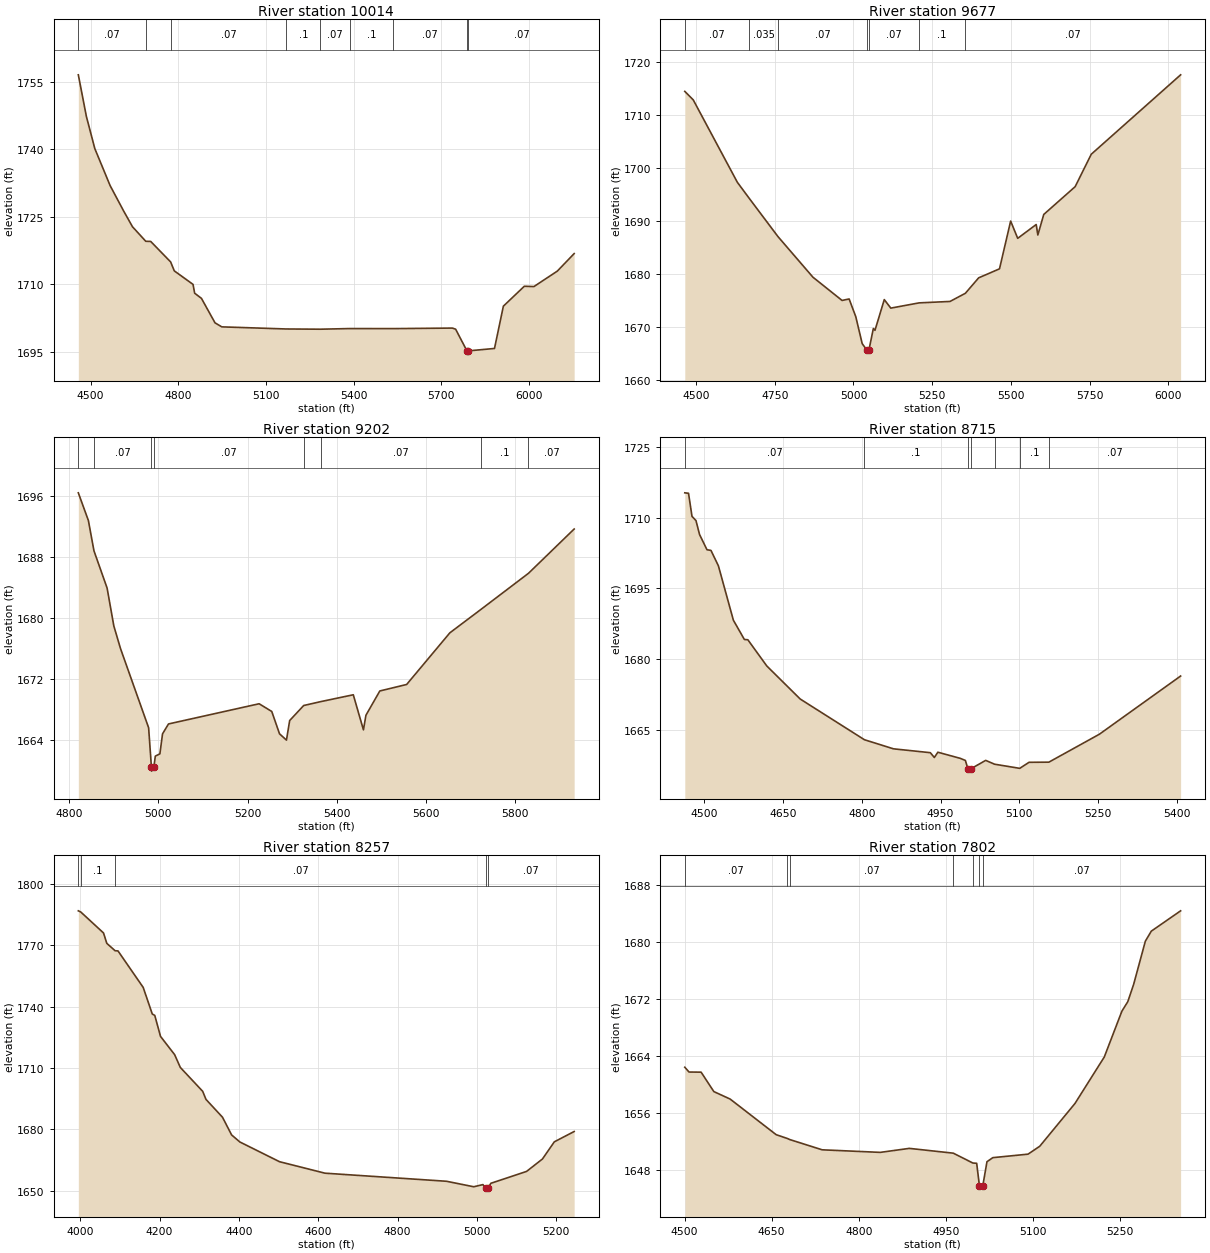
Type RM Length L Ch R = 1 ,10014   ,337,337,337
BEGIN DESCRIPTION:
Klein Hollow D
END DESCRIPTION:
XS GIS Cut Line= 5
      1940955.73     13867228.24      1941578.54     13867506.01
      1942151.46     13867699.15      1942546.43     13867610.18
      1942551.42     13867610.18
#Sta/Elev= 30
  4457.9 1756.56  4485.6 1747.26  4514.3 1740.16  4566.6 1731.94  4612.7 1726.31
  4643.2 1722.78  4688.6 1719.55  4705.6 1719.51  4773.8 1714.95  4786.2 1712.97
  4850.4 1709.96  4855.9    1708  4879.1 1706.86  4925.6 1701.41  4948.8 1700.52
  5168.8 1700.05  5286.2    1700  5386.4 1700.14  5535.6 1700.13  5737.6 1700.25
  5748.8    1700  5787.5 1695.18  5787.9 1694.68  5792.8 1695.18  5881.8 1695.72
  5912.1 1705.12  5983.8 1709.55  6016.7 1709.48  6096.6 1712.91  6154.3 1716.81
#Mann= 9 ,-1 , 0
  4457.9     .07       0  4688.6      .1       0  4773.8     .07       0
  5168.8      .1       0  5286.2     .07       0  5386.4      .1       0
  5535.6     .07       0  5787.5     .05       0  5792.8     .07       0
#XS Ineff= 2 , 0
         5680.11 1700.12
Permanent Ineff=
       F       F
Bank Sta=5787.5,5792.8
XS Rating Curve= 0 ,0
Exp/Cntr=0.3,0.1

Type RM Length L Ch R = 1 ,9677    ,475,475,475
BEGIN DESCRIPTION:
Klein Hollow 18.0
END DESCRIPTION:
XS GIS Cut Line= 4
      1941098.92     13867551.58        1941625.       13867675.
      1942244.78     13867835.87      1942581.64     13867632.64
#Sta/Elev= 30
  4464.5 1714.49  4491.3 1712.89  4631.3 1697.33  4668.1 1694.37  4760.4 1687.06
  4871.3  1679.4  4963.8 1675.01  4986.2 1675.29  5007.4 1671.93  5027.7 1666.85
  5043.5 1665.56  5043.9 1665.06  5048.8 1665.56  5063.1 1669.71  5068.3 1669.37
  5097.8 1675.17  5118.5 1673.56  5208.4 1674.55  5306.5 1674.82  5355.2 1676.36
  5397.5 1679.28  5463.6 1680.98    5499    1690  5521.4 1686.74  5580.1 1689.35
  5585.3 1687.37  5604.1 1691.25  5703.8  1696.5  5754.9 1702.62  6038.6 1717.62
#Mann= 7 ,-1 , 0
  4464.5     .07       0  4668.1    .035       0  4760.4     .07       0
  5043.5     .05       0  5048.8     .07       0  5208.4      .1       0
  5355.2     .07       0
Bank Sta=5043.5,5048.8
XS Rating Curve= 0 ,0
Exp/Cntr=0.3,0.1

Type RM Length L Ch R = 1 ,9202    ,487,487,487
BEGIN DESCRIPTION:
Klein Hollow 17.0
END DESCRIPTION:
XS GIS Cut Line= 3
      1941274.97     13867974.98        1941425.       13868075.
      1942270.36     13868469.03
#Sta/Elev= 30
  4820.2 1696.42  4842.8 1692.78  4855.3 1688.81  4884.8 1683.92  4899.9 1678.95
  4914.9 1675.98    4978 1665.59  4984.3  1660.4  4984.7  1659.9  4989.7  1660.4
    4993 1661.87  5003.3 1662.17  5009.2 1664.79  5022.6 1666.09    5226 1668.74
  5254.4 1667.73  5271.8  1664.8  5287.4 1663.97  5294.6 1666.54  5326.1 1668.51
  5365.1 1669.03  5437.4 1669.92  5460.2 1665.32  5465.8 1667.23    5497 1670.42
  5557.2 1671.27  5654.2 1678.05  5723.5  1681.1  5830.7 1685.86  5933.2 1691.67
#Mann= 8 ,-1 , 0
  4820.2    .035       0  4855.3     .07       0  4984.3     .05       0
  4989.7     .07       0  5326.1      .1       0  5365.1     .07       0
  5723.5      .1       0  5830.7     .07       0
Bank Sta=4984.3,4989.7
XS Rating Curve= 0 ,0
Exp/Cntr=0.3,0.1

Type RM Length L Ch R = 1 ,8715    ,458,458,458
BEGIN DESCRIPTION:
Klein Hollow 16.0
END DESCRIPTION:
XS GIS Cut Line= 3
      1941025.02     13868175.02        1941425.       13868525.
      1941825.01       13868625.
#Sta/Elev= 30
  4463.2 1715.28  4470.3 1715.18  4476.9 1710.29  4484.5 1709.39  4491.2 1706.47
  4505.4 1703.21    4513 1703.07  4527.2 1699.79  4555.7 1688.26  4576.6 1684.18
  4583.2 1684.12  4619.3 1678.56  4682.9 1671.55  4805.1 1662.92  4860.4 1660.99
  4930.6 1660.17  4938.2 1659.15  4944.9 1660.27  4987.6 1658.97  4997.3 1658.52
  5002.1 1656.76  5002.5 1656.26  5007.9 1656.76  5035.9 1658.54  5052.8 1657.73
  5100.8 1656.85  5118.4 1658.13  5156.2 1658.16  5252.4 1664.09    5407 1676.43
#Mann= 7 ,-1 , 0
  4463.2     .07       0  4805.1      .1       0  5002.1     .05       0
  5007.9      .1       0  5052.8     .07       0  5100.8      .1       0
  5156.2     .07       0
Bank Sta=5002.1,5007.9
XS Rating Curve= 0 ,0
Exp/Cntr=0.3,0.1

Type RM Length L Ch R = 1 ,8257    ,455,455,455
BEGIN DESCRIPTION:
Klein Hollow 15.0
END DESCRIPTION:
XS GIS Cut Line= 3
      1940725.04     13868325.03        1941525.       13868925.
      1941775.05       13868925.
#Sta/Elev= 30
  3995.2 1786.75  4001.3 1786.19  4058.7 1775.93    4067 1770.86  4087.9 1767.25
  4095.2 1767.16  4158.7 1749.34  4181.6 1736.34  4187.9 1735.66  4202.4 1725.39
  4237.9 1716.51  4252.4 1710.21  4308.7 1698.56    4317 1694.62  4358.7 1685.89
  4381.6 1677.26  4402.4 1673.81  4502.4 1664.17    4617 1658.56  4923.3 1654.61
    4992 1651.93  5015.2 1652.98  5022.3 1651.27  5022.7 1650.77  5028.1 1651.27
  5035.2 1653.62  5125.2 1659.42  5165.2 1665.48  5195.2 1673.88  5245.2 1678.92
#Mann= 5 ,-1 , 0
  3995.2     .07       0  4001.3      .1       0  4087.9     .07       0
  5022.3     .05       0  5028.1     .07       0
Bank Sta=5022.3,5028.1
XS Rating Curve= 0 ,0
Exp/Cntr=0.3,0.1

Type RM Length L Ch R = 1 ,7802    ,466,466,466
BEGIN DESCRIPTION:
Klein Hollow 14.0
END DESCRIPTION:
XS GIS Cut Line= 3
        1941025.       13869025.        1941425.       13869325.
      1941775.04     13869274.99
#Sta/Elev= 30
  4500.5 1662.45  4507.8 1661.78  4528.6 1661.76  4550.5 1659.04  4578.6 1657.99
  4657.8    1653  4677.3 1652.46  4681.1 1652.32    4737 1650.88    4837 1650.52
    4887 1651.08  4962.7 1650.41  4996.4 1649.03    5003 1648.99  5007.7 1645.87
  5008.2 1645.37  5013.1 1645.37  5013.6 1645.87  5020.7 1649.21  5030.8 1649.78
  5091.4 1650.27  5111.6 1651.38  5172.2 1657.37  5222.7 1663.89    5253 1670.31
  5263.1 1671.63  5273.2 1674.06  5293.4 1680.12  5303.6 1681.52  5354.1 1684.37
#Mann= 7 ,-1 , 0
  4500.5     .07       0  4677.3      .1       0  4681.1     .07       0
  4962.7    .033       0  4996.4     .07       0  5007.7     .05       0
  5013.6     .07       0
Bank Sta=5007.7,5013.6
XS Rating Curve= 0 ,0
Exp/Cntr=0.3,0.1

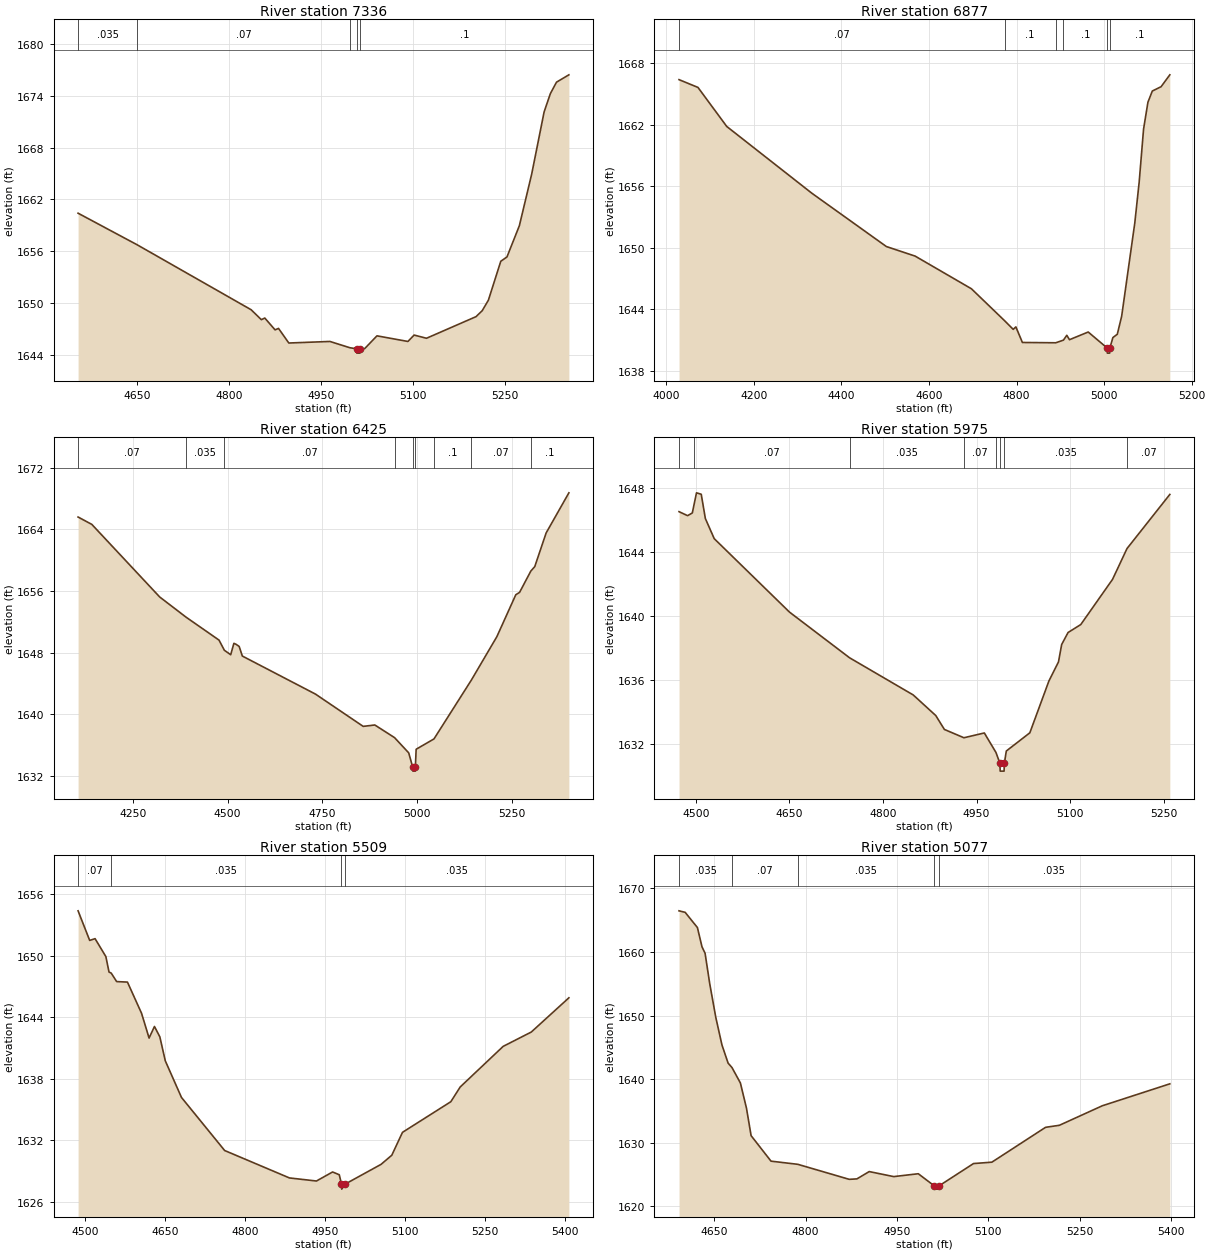
Type RM Length L Ch R = 1 ,7336    ,459,459,459
BEGIN DESCRIPTION:
Klein Hollow 13.0
END DESCRIPTION:
XS GIS Cut Line= 3
      1940975.04     13869575.02        1941375.       13869775.
      1941724.98       13869725.
#Sta/Elev= 30
  4553.4 1660.41  4649.9 1656.75  4835.7 1649.24  4852.4 1648.09    4858 1648.28
  4874.8 1646.91  4880.4 1647.08  4897.2 1645.39  4964.2 1645.57  4997.1 1644.84
  5007.7 1644.72  5008.2 1644.22  5013.1 1644.22  5013.6 1644.72  5020.8 1644.73
    5041 1646.22  5091.5 1645.57  5101.6 1646.31  5121.8 1645.94  5202.6 1648.44
  5212.7 1649.13  5222.8 1650.35    5243 1654.85  5253.1 1655.35  5273.3 1658.96
  5293.5 1664.96  5313.7 1672.13  5323.8 1674.23  5333.9 1675.57  5354.1 1676.42
#Mann= 5 ,-1 , 0
  4553.4    .035       0  4649.9     .07       0  4997.1      .1       0
  5007.7     .05       0  5013.6      .1       0
Bank Sta=5007.7,5013.6
XS Rating Curve= 0 ,0
Exp/Cntr=0.3,0.1

Type RM Length L Ch R = 1 ,6877    ,452,452,452
BEGIN DESCRIPTION:
Klein Hollow 12.0
END DESCRIPTION:
XS GIS Cut Line= 3
      1940724.96     13869624.97        1941525.       13870175.
      1941675.03       13870175.
#Sta/Elev= 30
  4029.1 1666.42  4072.4 1665.66  4138.1 1661.85  4332.3 1655.34  4502.7 1650.13
  4568.3  1649.2  4696.9 1646.01  4772.5  1642.9  4792.3 1642.05  4798.4 1642.29
  4813.3 1640.77  4889.5 1640.74  4907.1    1641  4914.7 1641.47  4920.8 1641.04
  4963.6 1641.79  5006.9 1640.23  5007.4 1639.73  5012.5 1639.73    5013 1640.23
    5020 1641.25    5030 1641.57    5040 1643.33    5070 1652.44    5080 1656.43
    5090 1661.59    5100 1664.22    5110 1665.31    5130 1665.73    5150 1666.89
#Mann= 6 ,-1 , 0
  4029.1     .07       0  4772.5      .1       0  4889.5     .07       0
  4907.1      .1       0  5006.9     .05       0    5013      .1       0
Bank Sta=5006.9,5013
XS Rating Curve= 0 ,0
Exp/Cntr=0.3,0.1

Type RM Length L Ch R = 1 ,6425    ,450,450,450
BEGIN DESCRIPTION:
Klein Hollow 11.0
END DESCRIPTION:
XS GIS Cut Line= 3
      1940575.02     13870175.01        1941375.       13870575.
        1941775.       13870575.
#Sta/Elev= 30
  4105.6 1665.62  4141.9 1664.66  4320.8 1655.24  4390.6 1652.61  4477.3 1649.64
  4491.4 1648.32  4508.1 1647.74  4516.5 1649.22    4522  1649.1  4530.4 1648.82
  4538.8 1647.57  4731.7 1642.63  4857.5 1638.44  4888.2 1638.62  4940.2 1636.98
  4977.6    1635  4988.2 1633.13  4988.7 1632.63  4994.6 1632.63  4995.1 1633.13
  4997.2 1635.47  5044.2 1636.81  5142.8 1644.45    5210 1650.08    5260 1655.53
    5270 1655.84  5299.6  1658.6    5310 1659.18    5340 1663.55    5400 1668.76
#Mann= 9 ,-1 , 0
  4105.6     .07       0  4390.6    .035       0  4491.4     .07       0
  4940.2    .035       0  4988.2    .035       0  4995.1    .035       0
  5044.2      .1       0  5142.8     .07       0  5299.6      .1       0
Bank Sta=4988.2,4995.1
XS Rating Curve= 0 ,0
Exp/Cntr=0.3,0.1

Type RM Length L Ch R = 1 ,5975    ,466,466,466
BEGIN DESCRIPTION:
Klein Hollow 10.0
END DESCRIPTION:
XS GIS Cut Line= 3
      1940875.02     13870575.02        1941225.       13870975.
      1941474.97     13870925.01
#Sta/Elev= 30
  4473.2 1646.52  4486.9 1646.27  4494.5 1646.44  4497.2 1646.95  4501.2  1647.7
  4508.8 1647.61  4515.4 1646.09  4529.6 1644.83  4650.2 1640.23  4746.4 1637.37
  4848.5 1635.04  4884.6 1633.75  4898.4 1632.88  4929.7 1632.36  4962.4 1632.66
    4981 1631.44  4987.3 1630.77  4987.8 1630.27    4994 1630.27  4994.5 1630.77
  4997.6 1631.53  5035.3 1632.67  5065.9 1635.92  5081.2 1637.11  5086.3  1638.2
  5096.5 1638.95  5116.9 1639.45  5167.8 1642.28    5191 1644.21  5259.6  1647.6
#Mann= 8 ,-1 , 0
  4473.2    .035       0  4497.2     .07       0  4746.4    .035       0
  4929.7     .07       0    4981    .035       0  4987.3    .035       0
  4994.5    .035       0    5191     .07       0
Bank Sta=4987.3,4994.5
XS Rating Curve= 0 ,0
Exp/Cntr=0.3,0.1

Type RM Length L Ch R = 1 ,5509    ,432,432,432
BEGIN DESCRIPTION:
Klein Hollow 9.0
END DESCRIPTION:
XS GIS Cut Line= 3
      1940613.53     13871290.37        1941125.       13871375.
      1941524.96       13871325.
#Sta/Elev= 30
  4486.6 1654.36  4508.4 1651.48  4518.5 1651.65  4538.8  1649.9  4544.7  1648.4
  4548.9 1648.29    4559 1647.47  4579.3 1647.42  4605.8 1644.38  4619.9 1641.97
    4630  1643.1  4640.1 1642.09  4650.3 1639.76  4680.7 1636.19  4761.8 1631.02
  4883.4 1628.35  4934.1 1628.05  4964.5 1628.93    4977 1628.66  4981.1 1627.76
  4981.6 1627.26  4988.4 1627.76  5055.4 1629.67  5075.6 1630.56  5095.7 1632.79
  5186.4 1635.77  5204.1 1637.21  5284.7 1641.16  5337.6 1642.56  5408.1 1645.89
#Mann= 4 ,-1 , 0
  4486.6     .07       0  4548.9    .035       0  4981.1    .035       0
  4988.4    .035       0
Bank Sta=4981.1,4988.4
XS Rating Curve= 0 ,0
Exp/Cntr=0.3,0.1

Type RM Length L Ch R = 1 ,5077    ,479,479,479
BEGIN DESCRIPTION:
Klein Hollow 8.0
END DESCRIPTION:
XS GIS Cut Line= 3
      1940625.02       13871825.        1941025.       13871775.
        1941425.       13871725.
#Sta/Elev= 30
    4592 1666.48  4602.1 1666.24  4622.2 1663.85  4629.8  1660.8  4634.8 1659.81
  4642.4 1655.04  4652.4 1649.72  4662.5 1645.39  4672.6 1642.53    4679 1641.83
  4692.8 1639.41  4702.8 1635.44  4710.4 1631.12  4743.1 1627.11  4787.2 1626.61
  4871.6 1624.25  4884.2 1624.32  4904.4 1625.47  4944.7 1624.68    4985 1625.13
  5011.5 1623.21    5012 1622.71  5018.4 1622.71  5018.9 1623.21  5075.7 1626.73
  5105.9 1626.95  5194.1 1632.43  5216.8 1632.75  5287.3 1635.82  5398.2 1639.27
#Mann= 5 ,-1 , 0
    4592    .035       0    4679     .07       0  4787.2    .035       0
  5011.5    .035       0  5018.9    .035       0
Bank Sta=5011.5,5018.9
XS Rating Curve= 0 ,0
Exp/Cntr=0.3,0.1

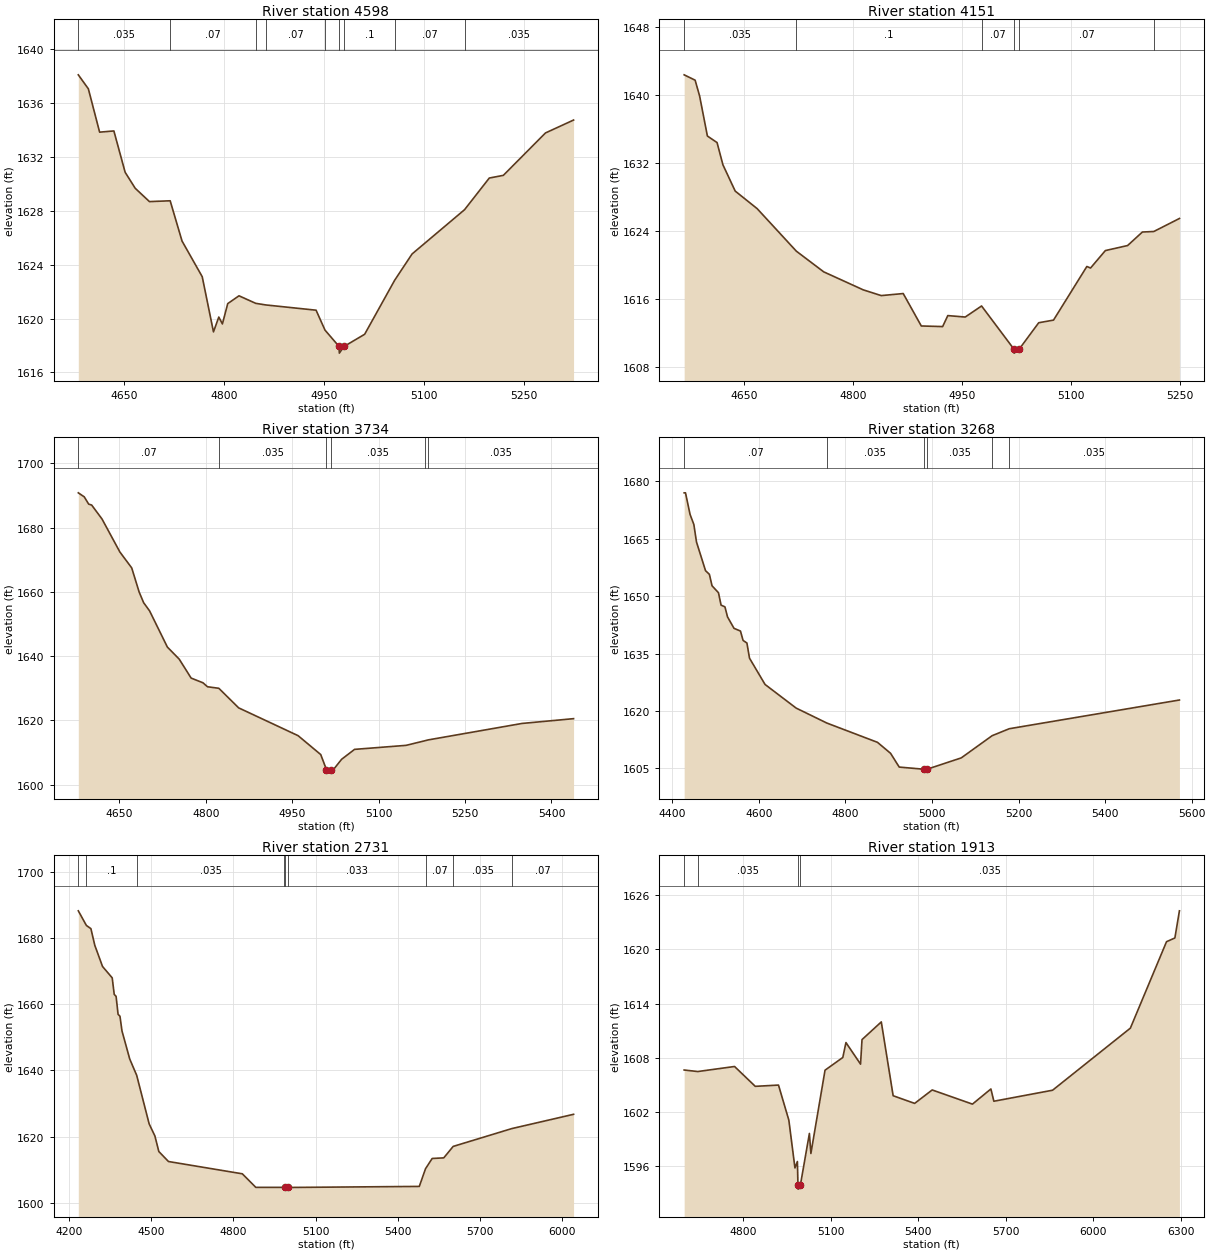
Type RM Length L Ch R = 1 ,4598    ,447,447,447
BEGIN DESCRIPTION:
Klein Hollow 7.0
END DESCRIPTION:
XS GIS Cut Line= 3
      1940725.01     13872075.01        1941125.       13872225.
      1941424.99       13872125.
#Sta/Elev= 30
  4581.4 1638.11  4596.5 1637.07  4613.4 1633.85  4634.8 1633.94  4651.7 1630.87
  4666.8 1629.68  4688.2 1628.69  4719.3 1628.75  4737.1 1625.76  4767.4 1623.11
  4784.3 1619.01  4792.3 1620.11  4797.7  1619.6  4805.7 1621.11  4822.6 1621.69
  4847.7 1621.13  4862.9 1621.01  4938.3 1620.62  4951.7 1619.14  4972.7 1617.93
  4973.2 1617.43  4980.4 1617.93  5011.2 1618.83  5056.2 1622.84  5082.4  1624.8
  5161.2 1628.09  5198.3 1630.44  5219.4 1630.64  5282.6 1633.79  5324.8 1634.75
#Mann= 9 ,-1 , 0
  4581.4    .035       0  4719.3     .07       0  4847.7      .1       0
  4862.9     .07       0  4951.7      .1       0  4972.7     .05       0
  4980.4      .1       0  5056.2     .07       0  5161.2    .035       0
Bank Sta=4972.7,4980.4
XS Rating Curve= 0 ,0
Exp/Cntr=0.3,0.1

Type RM Length L Ch R = 1 ,4151    ,417,417,417
BEGIN DESCRIPTION:
Klein Hollow 6.0
END DESCRIPTION:
XS GIS Cut Line= 3
      1940675.04     13872475.01        1941075.       13872625.
      1941324.99       13872575.
#Sta/Elev= 30
  4567.1 1642.33  4582.2  1641.7  4588.4 1639.84  4599.1 1635.14  4612.4 1634.37
  4620.5 1631.76  4637.4 1628.67  4667.6 1626.61  4721.6 1621.61  4759.3 1619.18
  4813.6 1617.07  4838.5 1616.39  4868.8 1616.63  4893.7 1612.82  4923.1 1612.75
  4930.2 1614.04  4954.2 1613.87  4976.7 1615.17    5021 1610.13  5021.5 1609.63
  5028.8 1610.13  5055.4  1613.2  5075.8 1613.51  5121.7 1619.81  5126.8 1619.63
  5147.2 1621.68  5177.8 1622.27  5198.2 1623.86  5213.9 1623.92  5249.2 1625.45
#Mann= 6 ,-1 , 0
  4567.1    .035       0  4721.6      .1       0  4976.7     .07       0
    5021     .05       0  5028.8     .07       0  5213.9    .035       0
Bank Sta=5021,5028.8
XS Rating Curve= 0 ,0
Exp/Cntr=0.3,0.1

Type RM Length L Ch R = 1 ,3734    ,466,466,466
BEGIN DESCRIPTION:
Klein Hollow 5.0
END DESCRIPTION:
XS GIS Cut Line= 3
      1940375.03     13872775.01        1940775.       13872875.
        1941175.       13873075.
#Sta/Elev= 30
  4578.9 1690.83  4589.2 1689.58  4596.9 1687.32  4602.1 1687.02  4620.1 1682.67
    4651 1672.43  4671.6 1667.46  4684.5 1659.95  4692.3 1656.63  4702.6 1654.09
  4733.5 1642.82  4754.1 1639.05  4774.7 1633.17  4795.3  1631.7  4803.1 1630.47
  4822.8 1629.99  4857.2  1623.9  4960.3 1615.25  4999.6 1609.37  5009.5 1604.71
    5010 1604.21  5017.5 1604.71  5021.9 1604.75  5035.9  1607.9  5058.3 1610.98
  5147.7 1612.23  5180.1 1613.65  5185.9 1613.92    5349 1619.05  5438.4 1620.54
#Mann= 6 ,-1 , 0
  4578.9     .07       0  4822.8    .035       0  5009.5    .035       0
  5017.5    .035       0  5180.1     .07       0  5185.9    .035       0
Bank Sta=5009.5,5017.5
XS Rating Curve= 0 ,0
Exp/Cntr=0.3,0.1

Type RM Length L Ch R = 1 ,3268    ,537,537,537
BEGIN DESCRIPTION:
Klein Hollow 4.0
END DESCRIPTION:
XS GIS Cut Line= 4
      1940374.97     13872924.96      1940604.03      13873259.7
        1940775.       13873275.      1941315.53     13873103.66
#Sta/Elev= 30
  4427.5 1677.03  4430.6 1677.03  4441.1  1671.4  4449.9 1668.75    4456 1664.17
  4476.9 1656.67  4485.8 1655.71  4491.9 1652.72  4506.8  1650.9  4512.8 1647.65
  4521.7 1647.21  4527.7 1644.58  4542.7 1641.58  4557.6 1640.88  4563.6 1638.43
  4572.5 1637.75  4578.5 1633.78  4614.4 1626.91  4686.2 1620.73  4757.3 1616.81
  4874.2 1611.77  4904.4  1608.9  4924.4  1605.3  4980.7 1604.74  4981.2 1604.24
  4988.7 1604.74  5067.7  1607.7  5139.1 1613.51  5178.7 1615.33  5571.8 1622.84
#Mann= 6 ,-1 , 0
  4427.5     .07       0  4757.3    .035       0  4980.7    .035       0
  4988.7    .035       0  5139.1     .07       0  5178.7    .035       0
Bank Sta=4980.7,4988.7
XS Rating Curve= 0 ,0
Exp/Cntr=0.3,0.1

Type RM Length L Ch R = 1 ,2731    ,818,818,818
BEGIN DESCRIPTION:
Klein Hollow 3.1
END DESCRIPTION:
XS GIS Cut Line= 4
      1940198.55     13873226.56       1940671.1      13873728.1
      1940868.28     13873822.67      1941749.73     13873653.58
#Sta/Elev= 30
  4235.1 1688.22  4264.6  1683.8    4281 1682.84  4295.2 1677.81  4323.5  1671.4
  4358.7 1667.97    4366 1662.99  4372.8 1662.39  4380.1 1656.96    4387 1656.37
  4394.3 1651.95  4422.6 1643.45  4447.9 1638.54  4493.4 1623.85  4514.4 1620.19
  4528.6 1615.51  4563.8 1612.49  4832.9 1608.78  4882.2 1604.68    4986 1604.68
  4989.4 1604.65  4989.9 1604.15    4998 1604.65  5478.1 1604.97  5500.7  1610.3
    5525 1613.41  5567.2 1613.59  5601.5 1617.05  5815.3 1622.44  6040.4 1626.75
#Mann= 9 ,-1 , 0
  4235.1     .07       0  4264.6      .1       0  4447.9    .035       0
    4986    .033       0  4989.4    .033       0    4998    .033       0
  5500.7     .07       0  5601.5    .035       0  5815.3     .07       0
Bank Sta=4989.4,4998
XS Rating Curve= 0 ,0
Exp/Cntr=0.3,0.1

Type RM Length L Ch R = 1 ,1913    ,483,483,483
BEGIN DESCRIPTION:
Klein Hollow 3.0
END DESCRIPTION:
XS GIS Cut Line= 4
      1940500.56     13874138.19        1940825.       13874375.
      1941365.73     13874467.41      1942100.29     13874331.35
#Sta/Elev= 30
  4598.3 1606.64  4644.9 1606.47    4771 1607.03    4842 1604.83  4921.6 1604.97
  4957.1 1601.08    4978 1595.79  4986.4  1596.5  4988.3 1593.94  4988.8 1593.44
  4996.9 1593.94  5027.5 1599.61  5032.6 1597.39  5081.1 1606.62    5142 1608.03
  5152.8 1609.68  5202.8 1607.29  5207.8 1610.01  5273.9 1611.97  5314.5 1603.79
  5388.2 1602.94  5448.3 1604.43  5586.3 1602.86  5649.5 1604.54  5659.7 1603.18
  5860.9  1604.4  6127.5 1611.28  6251.4 1620.86    6280 1621.27  6295.6 1624.28
#Mann= 4 ,-1 , 0
  4598.3     .07       0  4644.9    .035       0  4988.3    .035       0
  4996.9    .035       0
Bank Sta=4988.3,4996.9
XS Rating Curve= 0 ,0
Exp/Cntr=0.3,0.1