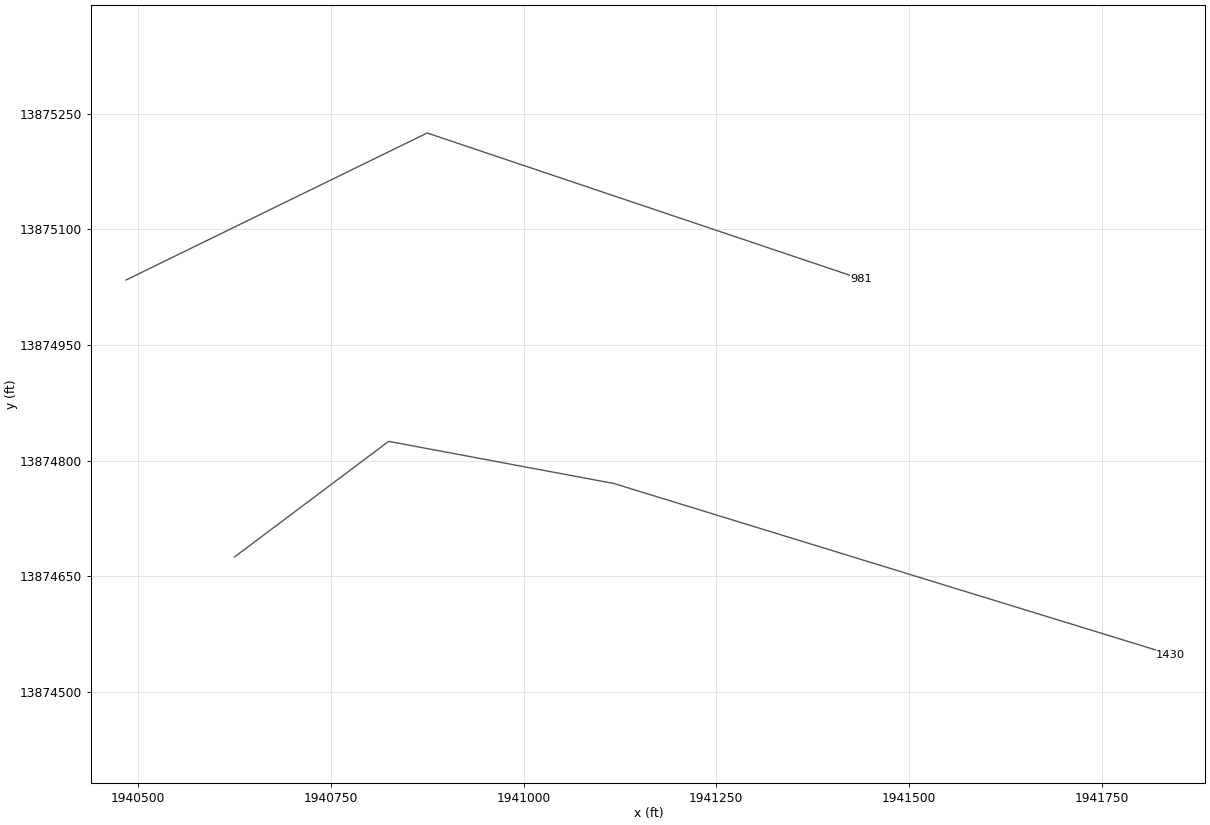
HEC-RAS study Klein Hollow.prj: Klein Hollow Base Level Engineering

--- Klein Hollow.g01 (geometry) --- (continued)

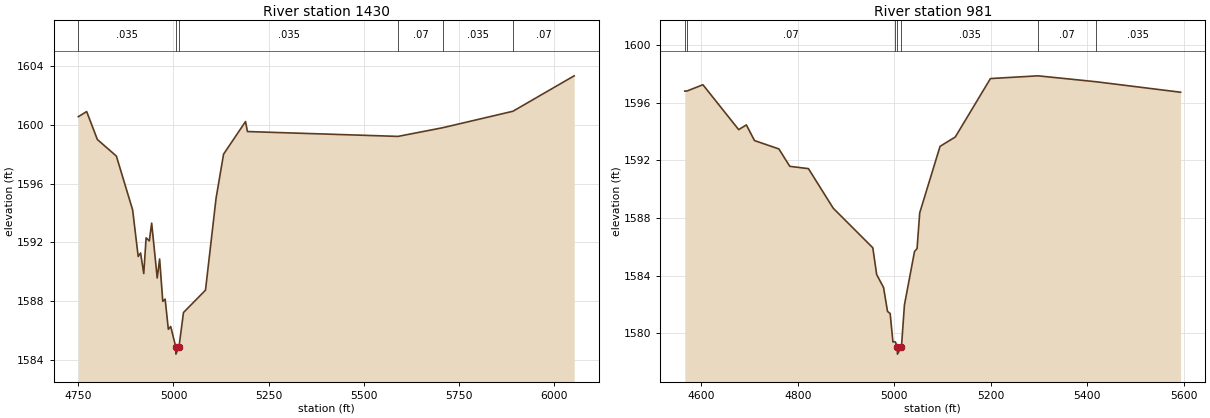
Type RM Length L Ch R = 1 ,1430    ,449,449,449
BEGIN DESCRIPTION:
Klein Hollow 2.0
END DESCRIPTION:
XS GIS Cut Line= 4
      1940624.99     13874674.99        1940825.       13874825.
      1941117.17     13874770.36      1941839.41     13874548.49
#Sta/Elev= 30
    4750 1600.55  4771.9  1600.9    4800    1599    4850 1597.87  4892.7 1594.21
  4907.3 1591.04  4913.6 1591.28  4921.9 1589.88  4928.1 1592.31  4936.5  1592.1
  4942.7 1593.31  4957.3 1589.58  4963.6 1590.87  4971.9 1587.99  4978.1 1588.14
  4986.5 1586.09  4992.7 1586.28  5005.9  1584.9  5006.4  1584.4  5014.5  1584.9
  5026.3 1587.23  5084.1 1588.75  5111.9    1595  5131.6    1598  5189.3 1600.22
  5194.4 1599.54  5589.9 1599.21  5707.5  1599.8  5891.9 1600.92  6052.8 1603.33
#Mann= 6 ,-1 , 0
    4750    .035       0  5005.9    .035       0  5014.5    .035       0
  5589.9     .07       0  5707.5    .035       0  5891.9     .07       0
Bank Sta=5005.9,5014.5
XS Rating Curve= 0 ,0
Exp/Cntr=0.3,0.1

Type RM Length L Ch R = 1 ,981     ,0,0,0
BEGIN DESCRIPTION:
Klein Hollow 1.0
END DESCRIPTION:
XS GIS Cut Line= 3
      1940484.52     13875034.36        1940875.       13875225.
      1941437.93      13875035.5
#Sta/Elev= 30
  4565.5 1596.82  4570.4 1596.83  4603.1 1597.26  4677.3 1594.14  4693.2 1594.47
  4710.1 1593.38  4760.7  1592.8  4783.3 1591.59    4822 1591.43  4873.4 1588.68
  4955.5 1585.93  4963.5 1584.07  4977.8 1583.17    4986 1581.51  4991.5 1581.36
  4997.2 1579.39  5002.3 1579.39  5006.1 1579.04  5006.6 1578.54  5014.9 1579.04
  5021.1 1581.96    5042 1585.67  5047.3 1585.88  5052.8 1588.36    5095 1592.98
  5126.6 1593.63  5199.5 1597.69  5298.1 1597.88  5418.3 1597.47    5594 1596.74
#Mann= 7 ,-1 , 0
  4565.5      .1       0  4570.4     .07       0  5002.3    .035       0
  5006.1    .035       0  5014.9    .035       0  5298.1     .07       0
  5418.3    .035       0
Bank Sta=5006.1,5014.9
XS Rating Curve= 0 ,0
Exp/Cntr=0.3,0.1

Chan Stop Cuts=-1
Use User Specified Reach Order=0
Composite Channel Slope=5