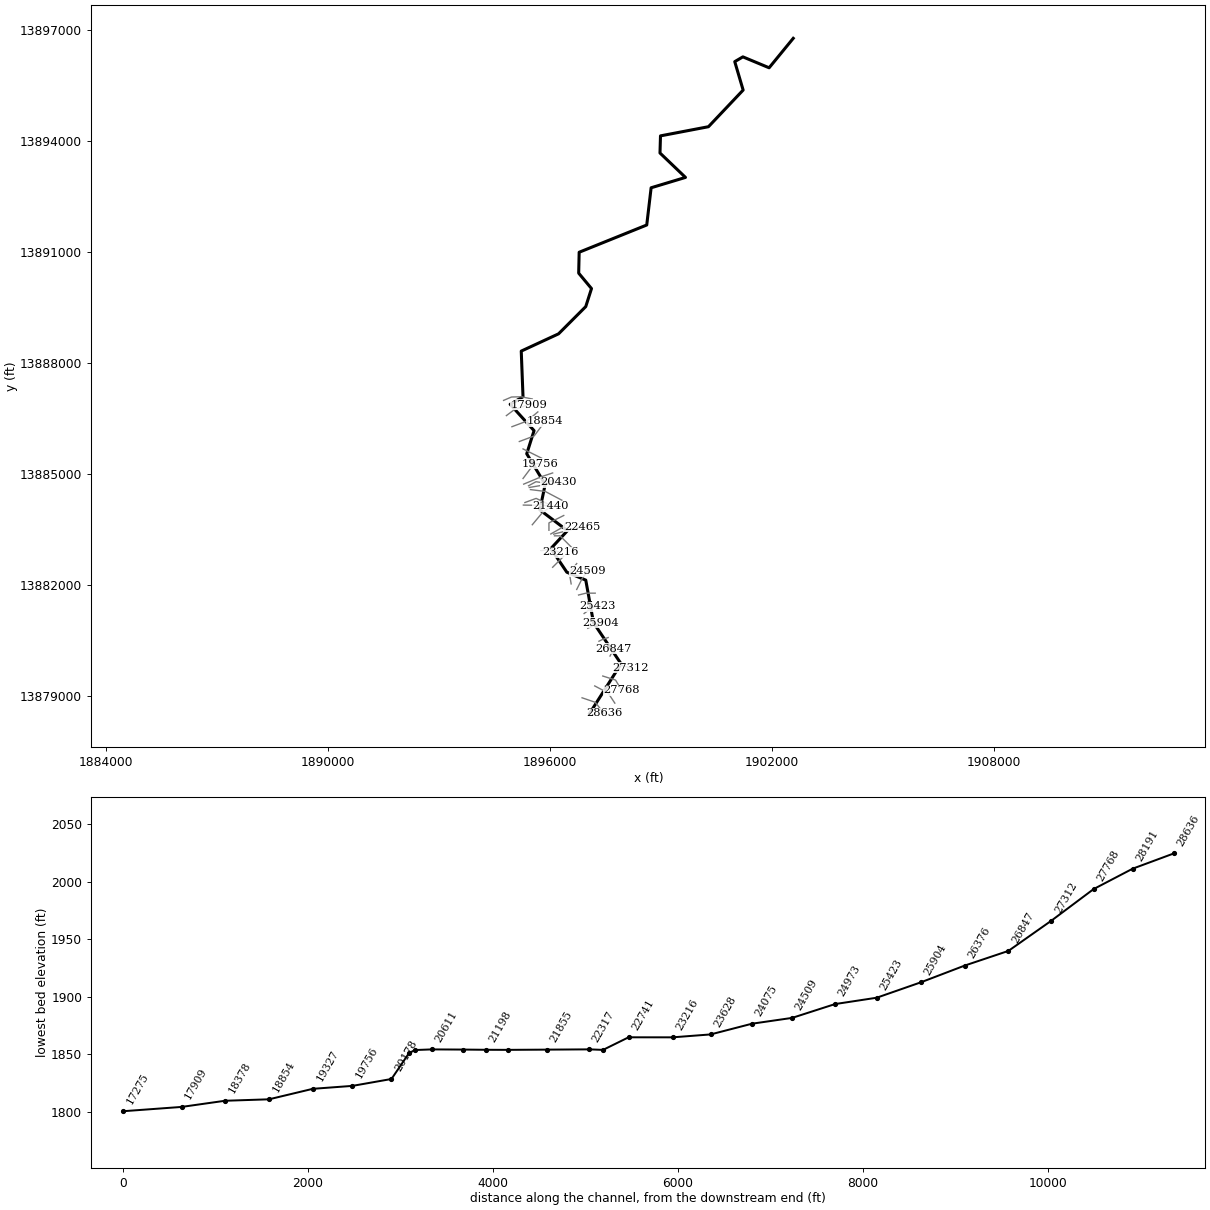
--- Lambs Creek.prj (project) ---

Proj Title=Lambs Creek Base Level Engineering
Current Plan=p01
Default Exp/Contr=0.3,0.1
English Units
Geom File=g01
Flow File=f01
Plan File=p01
Y Axis Title=Elevation
X Axis Title(PF)=Main Channel Distance
X Axis Title(XS)=Station
BEGIN DESCRIPTION:
Lambs Creek
END DESCRIPTION:
DSS Export Rating Curves= 0
DSS Export Rating Curve Sorted= 0
DSS Export Volume Flow Curves= 0
DXF OffsetX= 0
DXF OffsetY= 0
DXF ScaleX= 1
DXF ScaleY= 10

--- Lambs Creek.p01 (plan) ---

Plan Title=Multiple Run
Short Identifier=Multiple
Geom File=g01
Flow File=f01
Subcritical Flow
K Sum by GR= 0
Std Step Tol= 0.01
Critical Tol= 0.01
Num of Std Step Trials= 20
Max Error Tol= 0.3
Flow Tol Ratio= 0.001
Split Flow NTrial= 30
Split Flow Tol= 0.02
Split Flow Ratio= 0.02
Log Output Level= 0
Friction Slope Method= 1
Unsteady Friction Slope Method= 2
Unsteady Bridges Friction Slope Method= 1
Parabolic Critical Depth
Global Vel Dist=  1 , 1 , 1
Global Log Level= 0
CheckData=True
Encroach Param= -1, 0, 0, 0
BEGIN DESCRIPTION:
Multiple Run
END DESCRIPTION:

--- Lambs Creek.f01 (steady flow) ---

Flow Title=Multiple
Number of Profiles=7
Profile Names=10-year,25-year,50-year,1pct_min,100-year,1pct_plu,500-year
River Rch & RM= Lambs Creek,Reach-1,28636
     397     626     829     534    1065    2125    1726
River Rch & RM= Lambs Creek,Reach-1,27312
    1615    2801    3952    2696    5380   10734    9836
River Rch & RM= Lambs Creek,Reach-1,22741
    2241    3941    5610    3853    7688   15340   14264
River Rch & RM= Lambs Creek,Reach-1,16517
    3971    7214   10494    7351   14667   29265   28333
River Rch & RM= Lambs Creek,Reach-1,14568
    4129    7497   10900    7630   15223   30375   29363
River Rch & RM= Lambs Creek,Reach-1,11572
    4223    7664   11139    7793   15549   31024   29958
River Rch & RM= Lambs Creek,Reach-1,9725
    4370    7940   11546    8081   16125   32173   31095
River Rch & RM= Lambs Creek,Reach-1,8607
    4579    8326   12115    8482   16924   33768   32658
River Rch & RM= Lambs Creek,Reach-1,6124
    4752    8629   12544    8771   17500   34917   33682
Boundary for River Rch & Prof#=Lambs Creek,Reach-1,1
Up Type=0
Dn Type=3
Dn Slope=0.005
Boundary for River Rch & Prof#=Lambs Creek,Reach-1,2
Up Type=0
Dn Type=3
Dn Slope=0.005
Boundary for River Rch & Prof#=Lambs Creek,Reach-1,3
Up Type=0
Dn Type=3
Dn Slope=0.005
Boundary for River Rch & Prof#=Lambs Creek,Reach-1,4
Up Type=0
Dn Type=3
Dn Slope=0.005
Boundary for River Rch & Prof#=Lambs Creek,Reach-1,5
Up Type=0
Dn Type=3
Dn Slope=0.005
Boundary for River Rch & Prof#=Lambs Creek,Reach-1,6
Up Type=0
Dn Type=3
Dn Slope=0.005
Boundary for River Rch & Prof#=Lambs Creek,Reach-1,7
Up Type=0
Dn Type=3
Dn Slope=0.005

--- Lambs Creek.g01 (geometry) ---

Geom Title=Existing Conditions
Program Version=4.10

River Reach=Lambs Creek     ,Reach-1
Reach XY= 30
        1897075.       13878525.      1897923.64     13879865.35
      1897178.75     13880976.55      1896969.64      13882127.7
      1896458.24     13882341.43      1896027.14     13882980.97
      1896474.45     13883464.36      1895728.68     13884026.58
      1895873.62     13884715.34      1895375.07     13885543.23
      1895572.76     13886169.07      1894926.74     13886881.16
      1895274.32      13887084.6      1895226.73     13888319.38
      1896234.99     13888786.26      1896969.48     13889522.57
      1897124.63     13890009.73      1896778.54     13890426.46
      1896791.43     13890991.76      1898616.97     13891728.47
      1898735.43     13892734.79      1899664.05       13893015.
        1898975.       13893675.      1898988.62     13894138.22
      1900284.68     13894385.76      1901221.48     13895376.46
      1900994.78     13896145.09      1901214.52     13896274.07
      1901923.45     13895978.75        1902575.       13896775.

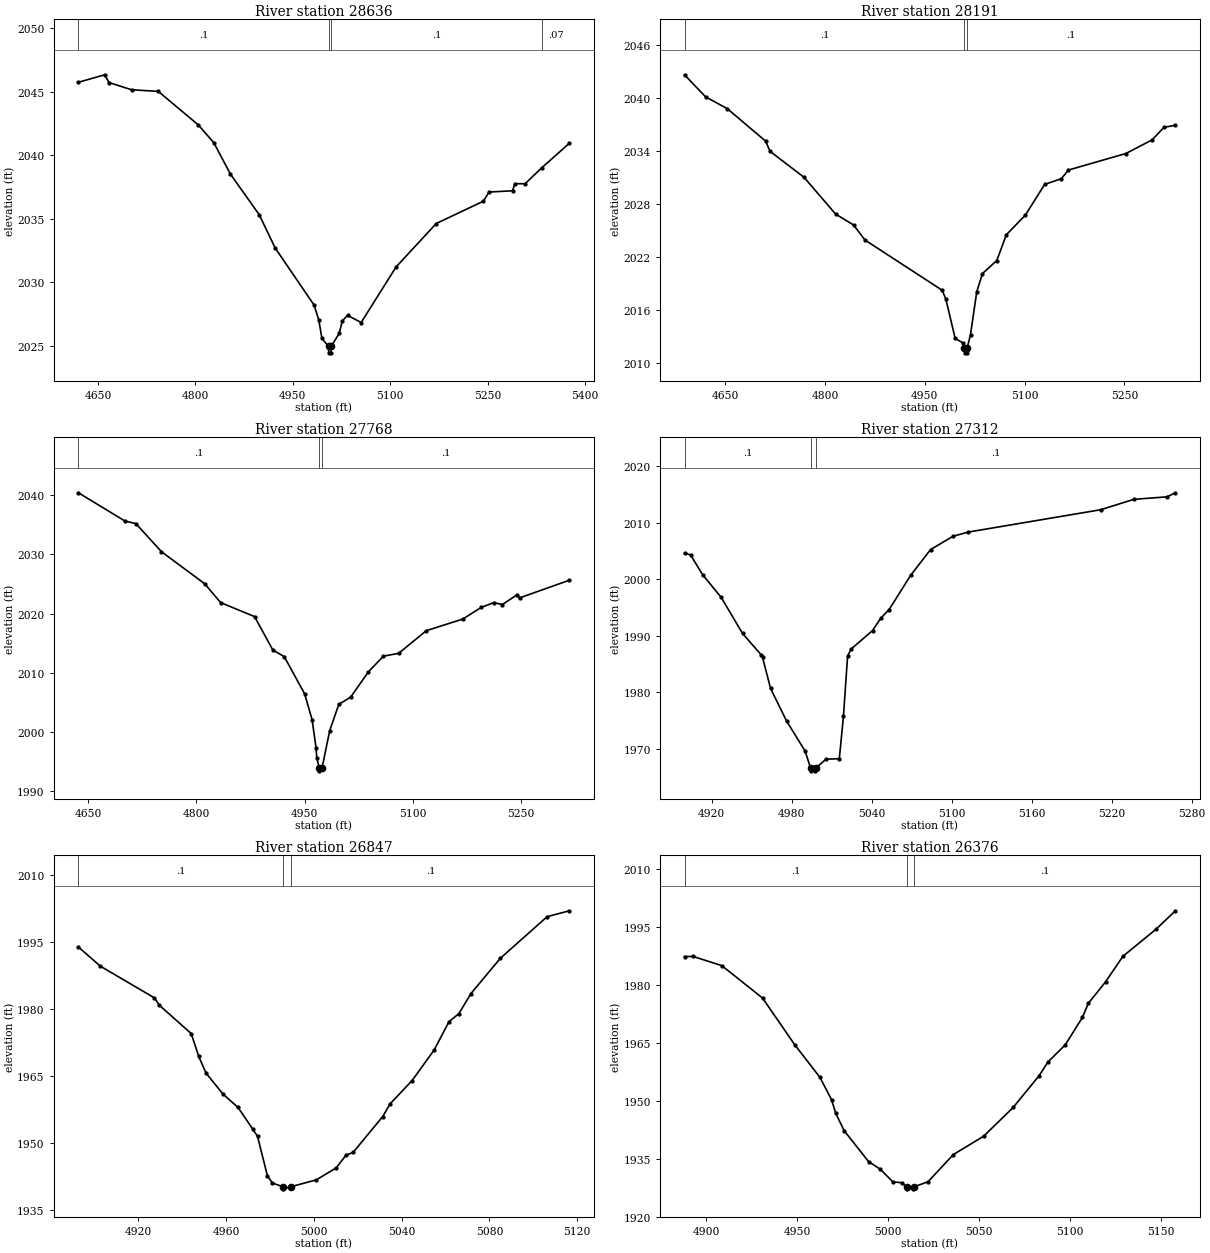
Type RM Length L Ch R = 1 ,28636   ,445,445,445
BEGIN DESCRIPTION:
Lamb Creek 61.0
END DESCRIPTION:
XS GIS Cut Line= 3
      1896870.05     13878946.34        1897225.       13878825.
      1897461.62     13878526.27
#Sta/Elev= 30
  4619.8 2045.75  4660.5 2046.34  4666.8 2045.73  4701.7 2045.16  4742.9 2045.03
  4804.7 2042.38  4828.5 2040.98  4853.9 2038.52  4898.3 2035.32  4922.9 2032.69
  4982.9 2028.19  4990.2    2027  4994.9 2025.57  5005.1 2024.93  5005.3 2024.43
  5008.8 2024.43  5009.1 2024.93  5021.6 2025.97  5026.4 2026.96  5034.5 2027.38
  5055.4 2026.82  5109.2  2031.2    5171 2034.62  5243.7 2036.38  5252.3  2037.1
  5288.6  2037.2  5292.1 2037.76  5307.8 2037.75  5333.3    2039    5376 2040.94
#Mann= 4 ,-1 , 0
  4619.8      .1       0  5005.1     .05       0  5009.1      .1       0
  5333.3     .07       0
Bank Sta=5005.1,5009.1
XS Rating Curve= 0 ,0
Exp/Cntr=0.3,0.1

Type RM Length L Ch R = 1 ,28191   ,423,423,423
BEGIN DESCRIPTION:
Lamb Creek 60.0
END DESCRIPTION:
XS GIS Cut Line= 3
      1897211.79       13879267.        1897575.       13879075.
      1897754.96     13878801.66
#Sta/Elev= 30
  4588.7 2042.59  4620.3  2040.1  4652.9 2038.77  4710.6  2035.1  4717.4 2033.94
  4768.3 2031.02  4815.8 2026.87  4842.9 2025.63  4859.9 2023.94    4976 2018.27
  4981.6 2017.27  4995.6 2012.83  5007.9  2012.3  5009.5  2011.7  5009.8  2011.2
  5013.3  2011.2  5013.5  2011.7  5018.7 2013.26  5028.1  2018.1  5036.7 2020.15
  5058.2 2021.62  5072.6 2024.53  5101.3 2026.76  5130.1 2030.21  5155.2 2030.86
    5166 2031.84  5252.2  2033.7  5291.7 2035.24  5309.6 2036.66  5326.8 2036.89
#Mann= 3 ,-1 , 0
  4588.7      .1       0  5009.5     .05       0  5013.5      .1       0
Bank Sta=5009.5,5013.5
XS Rating Curve= 0 ,0
Exp/Cntr=0.3,0.1

Type RM Length L Ch R = 1 ,27768   ,456,456,456
BEGIN DESCRIPTION:
Lamb Creek 59.0
END DESCRIPTION:
XS GIS Cut Line= 3
      1897428.85     13879535.08        1897775.       13879425.
      1897936.97     13879152.77
#Sta/Elev= 30
  4636.5 2040.37  4701.2 2035.59    4716 2035.18  4751.6 2030.43  4811.4 2025.03
  4833.5 2021.85  4880.5 2019.49  4905.9 2013.84  4921.6 2012.74  4949.9 2006.45
  4960.2  2002.1  4965.7 1997.36  4966.7 1995.69    4970 1993.97  4970.2 1993.47
    4974 1993.97  4984.6 2000.25  4997.2 2004.68  5013.7 2005.91  5038.2 2010.17
  5059.1 2012.82    5080 2013.28  5118.4 2017.11  5168.7 2019.06  5194.4 2021.03
    5212 2021.85  5223.7 2021.51  5244.1 2023.17  5247.6 2022.64  5316.5 2025.62
#Mann= 3 ,-1 , 0
  4636.5      .1       0    4970     .05       0    4974      .1       0
Bank Sta=4970,4974
XS Rating Curve= 0 ,0
Exp/Cntr=0.3,0.1

Type RM Length L Ch R = 1 ,27312   ,465,465,465
BEGIN DESCRIPTION:
Lamb Creek 58.0
END DESCRIPTION:
XS GIS Cut Line= 3
      1897825.03       13879825.        1897925.       13879825.
      1898183.61     13879753.81
#Sta/Elev= 30
  4899.6 2004.58  4904.1 2004.29  4913.1  2000.8  4927.1 1996.76  4943.1 1990.39
  4957.1  1986.6  4958.1 1986.18  4964.1 1980.68  4976.1 1974.92  4990.1 1969.57
  4994.1 1966.59  4994.3 1966.09  4997.8 1966.09  4998.1 1966.59  5005.7 1968.15
  5015.7 1968.24  5018.8 1975.72  5021.9 1986.37  5024.6 1987.64  5040.6 1990.89
  5046.8 1993.09    5053 1994.59  5069.2 2000.66  5084.1 2005.21  5100.9 2007.56
  5112.1  2008.3  5211.7 2012.26  5236.6  2014.1  5261.5 2014.54  5267.8 2015.26
#Mann= 3 ,-1 , 0
  4899.6      .1       0  4994.1     .05       0  4998.1      .1       0
Bank Sta=4994.1,4998.1
XS Rating Curve= 0 ,0
Exp/Cntr=0.3,0.1

Type RM Length L Ch R = 1 ,26847   ,471,471,471
BEGIN DESCRIPTION:
Lamb Creek 57.0
END DESCRIPTION:
XS GIS Cut Line= 3
      1897625.02     13880075.03        1897675.       13880175.
      1897725.01     13880275.03
#Sta/Elev= 30
  4892.8 1993.89  4902.8 1989.61  4927.4 1982.53  4929.7 1980.87  4944.2 1974.54
  4947.6 1969.44  4950.9 1965.74  4958.7    1961  4965.5 1958.03  4972.2 1953.21
  4974.4 1951.54  4978.9 1942.73  4981.2 1941.13  4985.8 1940.34    4986 1939.84
  4989.8 1940.34  5001.2 1941.85  5010.2 1944.52  5014.6 1947.32    5018 1948.02
  5031.4 1955.99  5034.8 1958.85  5044.8 1964.05  5054.9 1970.92  5061.6 1977.21
  5066.1    1979  5071.6 1983.49    5085 1991.38  5106.3 2000.67  5116.4 2001.99
#Mann= 3 ,-1 , 0
  4892.8      .1       0  4985.8     .05       0  4989.8      .1       0
Bank Sta=4985.8,4989.8
XS Rating Curve= 0 ,0
Exp/Cntr=0.3,0.1

Type RM Length L Ch R = 1 ,26376   ,472,472,472
BEGIN DESCRIPTION:
Lamb Creek 56.0
END DESCRIPTION:
XS GIS Cut Line= 3
      1897325.02     13880475.01        1897425.       13880525.
        1897575.       13880575.
#Sta/Elev= 30
  4888.2 1987.29    4893  1987.3  4908.7 1984.93  4931.1 1976.54  4948.9 1964.38
  4962.6 1956.05  4969.1 1950.19  4971.3 1946.73    4976 1942.19  4989.4 1934.22
  4995.9 1932.21  5002.7 1928.98  5007.5 1928.74  5010.3 1927.66  5010.5 1927.16
    5014 1927.16  5014.3 1927.66  5022.1 1929.01    5036 1936.03  5052.6 1940.76
  5068.9 1948.23  5083.1 1956.42    5088 1959.98  5097.5 1964.42    5107 1971.56
  5110.2 1975.16  5119.7 1980.74  5129.2 1987.34  5147.4 1994.34  5158.1 1999.13
#Mann= 3 ,-1 , 0
  4888.2      .1       0  5010.3     .05       0  5014.3      .1       0
Bank Sta=5010.3,5014.3
XS Rating Curve= 0 ,0
Exp/Cntr=0.3,0.1

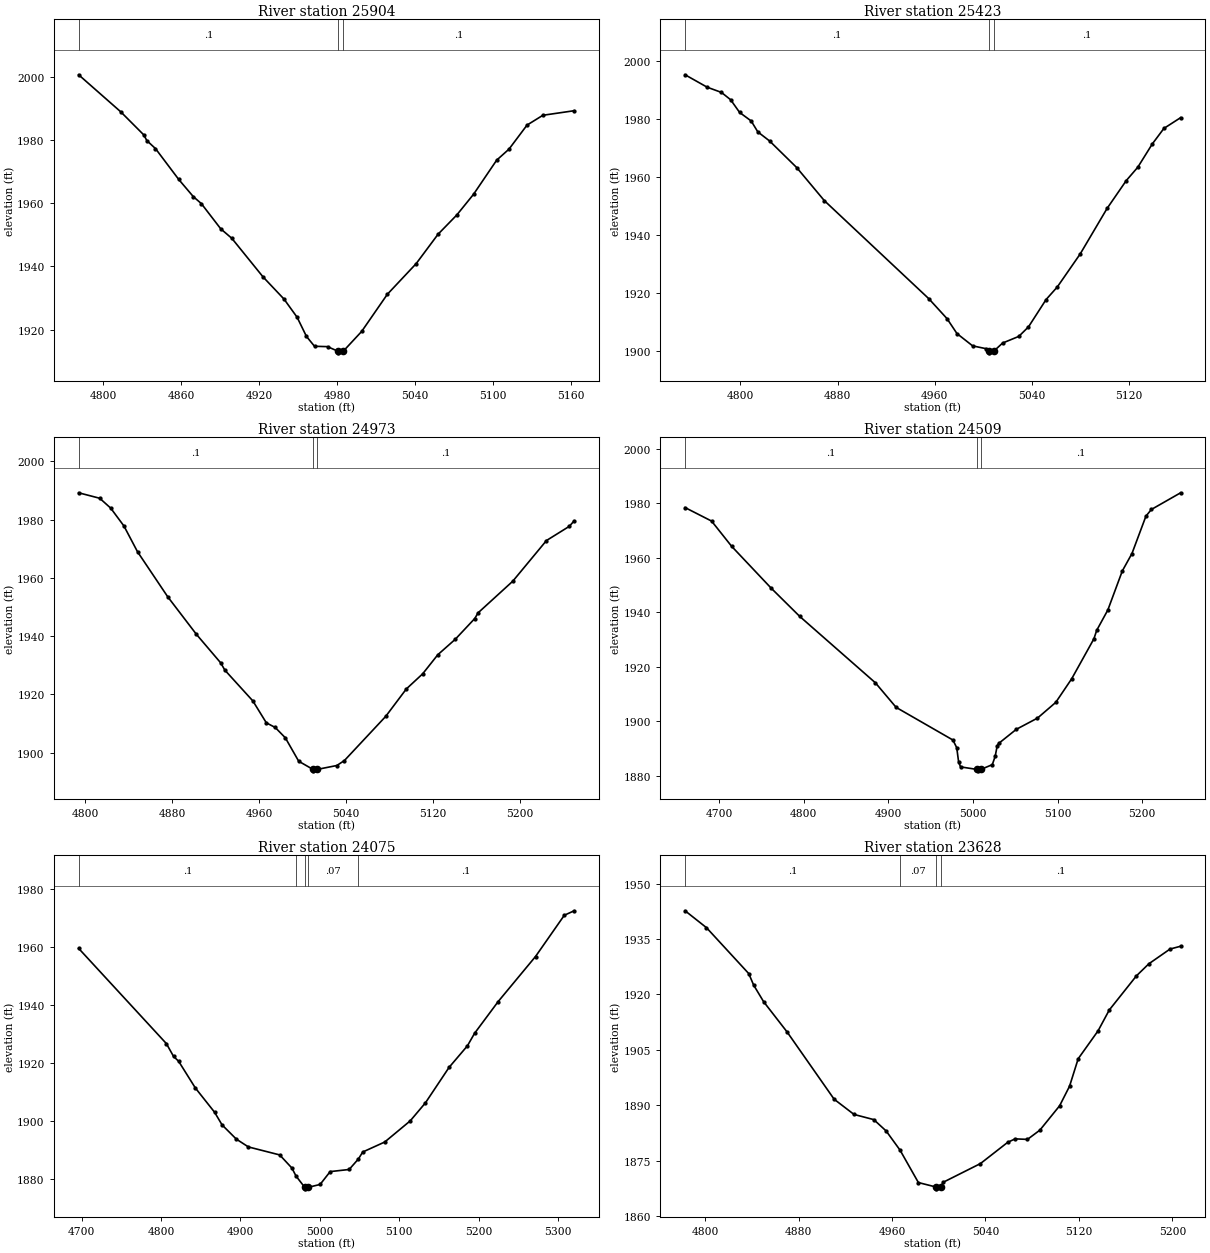
Type RM Length L Ch R = 1 ,25904   ,481,481,481
BEGIN DESCRIPTION:
Lamb Creek 55.0
END DESCRIPTION:
XS GIS Cut Line= 3
      1897025.03     13880825.02        1897225.       13880925.
      1897375.02     13880975.01
#Sta/Elev= 30
    4781 2000.58  4813.4 1988.89  4831.3 1981.53  4833.5 1979.79  4840.2 1977.25
  4858.1  1967.5  4869.3 1962.08  4875.5 1959.87  4890.5 1951.87    4899 1948.89
    4923 1936.71  4939.2 1929.68  4949.3 1923.93  4956.5 1917.87  4962.7 1914.76
  4972.7 1914.65  4980.8 1913.19  4981.1 1912.69  4984.8 1913.19    4999 1919.45
  5018.8  1931.2    5041 1940.89  5057.9  1950.2  5072.2 1956.22  5085.2 1962.81
    5103 1973.59  5112.5 1977.08  5126.4 1984.68  5138.6 1987.78  5162.7 1989.22
#Mann= 3 ,-1 , 0
    4781      .1       0  4980.8     .05       0  4984.8      .1       0
Bank Sta=4980.8,4984.8
XS Rating Curve= 0 ,0
Exp/Cntr=0.3,0.1

Type RM Length L Ch R = 1 ,25423   ,450,450,450
BEGIN DESCRIPTION:
Lamb Creek 54.0
END DESCRIPTION:
XS GIS Cut Line= 3
      1896925.02     13881225.01        1897125.       13881375.
      1897275.01       13881425.
#Sta/Elev= 30
  4754.4 1995.35  4772.6 1991.05  4784.3 1989.26  4791.9 1986.72  4799.3 1982.33
  4808.8 1979.39  4814.3  1975.6    4824 1972.46  4846.3 1963.28    4869 1951.87
  4955.1 1917.94  4970.1 1911.05  4978.3 1905.88  4991.2 1901.63  5001.9 1900.69
  5004.4 1899.72  5004.6 1899.22  5008.4 1899.72  5015.9 1902.61  5029.2  1904.9
  5037.2  1908.2  5051.7 1917.65  5060.9 1921.98  5079.8 1933.42  5101.9 1949.13
  5117.7 1958.76  5127.2 1963.38  5139.2 1971.46  5148.7  1976.8  5162.5 1980.53
#Mann= 3 ,-1 , 0
  4754.4      .1       0  5004.4     .05       0  5008.4      .1       0
Bank Sta=5004.4,5008.4
XS Rating Curve= 0 ,0
Exp/Cntr=0.3,0.1

Type RM Length L Ch R = 1 ,24973   ,464,464,464
BEGIN DESCRIPTION:
Lamb Creek 53.0
END DESCRIPTION:
XS GIS Cut Line= 3
      1896774.96     13881724.99        1896975.       13881775.
      1897225.01       13881775.
#Sta/Elev= 30
  4793.9 1989.22  4813.3 1987.34  4823.4 1983.96  4835.6 1977.82  4848.1 1968.97
  4875.9 1953.51  4902.4 1940.57  4924.7  1930.8  4928.5 1928.31  4954.3 1917.73
  4966.7 1910.21  4974.9 1908.61  4984.2 1905.06  4996.5 1897.02  5009.6 1894.22
  5009.9 1893.72  5013.6 1894.22  5031.6 1895.55  5038.6 1897.26  5076.6 1912.42
  5095.6 1921.85  5110.6 1927.03  5124.6 1933.61  5140.6 1938.89  5158.6 1946.04
  5161.6 1947.97  5193.6 1958.86  5224.6 1972.82  5245.6 1977.69  5250.1 1979.58
#Mann= 3 ,-1 , 0
  4793.9      .1       0  5009.6     .05       0  5013.6      .1       0
Bank Sta=5009.6,5013.6
XS Rating Curve= 0 ,0
Exp/Cntr=0.3,0.1

Type RM Length L Ch R = 1 ,24509   ,434,434,434
BEGIN DESCRIPTION:
Lamb Creek 52.0
END DESCRIPTION:
XS GIS Cut Line= 3
      1896724.98     13881874.96        1896875.       13882175.
      1897024.97     13882374.96
#Sta/Elev= 30
    4660 1978.46  4691.3  1973.5  4714.9 1964.26  4761.6 1948.88  4795.4 1938.48
  4884.8 1914.08  4909.3 1905.05  4976.4 1893.05  4980.9 1890.22  4983.1 1885.03
  4985.4 1883.18  5005.2 1882.23  5005.5 1881.73  5009.2 1882.23  5022.9    1884
  5026.3 1887.04  5028.7 1890.93  5030.4 1891.79  5051.3 1896.99  5076.3 1901.11
  5097.9 1906.89  5116.7 1915.56  5142.9 1930.22  5146.3 1933.39  5159.4 1940.83
  5176.5 1955.18  5187.9 1961.58  5204.4 1975.31  5210.8 1977.76  5245.4  1983.9
#Mann= 3 ,-1 , 0
    4660      .1       0  5005.2     .05       0  5009.2      .1       0
Bank Sta=5005.2,5009.2
XS Rating Curve= 0 ,0
Exp/Cntr=0.3,0.1

Type RM Length L Ch R = 1 ,24075   ,447,447,447
BEGIN DESCRIPTION:
Lamb Creek 51.0
END DESCRIPTION:
XS GIS Cut Line= 3
      1896575.01     13882024.97        1896525.       13882325.
      1896724.98     13882574.98
#Sta/Elev= 30
  4696.2 1959.55  4806.7 1926.75  4815.8 1922.32  4822.2 1920.64  4843.2 1911.46
  4867.5 1903.07  4876.9 1898.72  4894.9 1893.81  4910.1 1891.12  4949.5 1888.37
  4964.9 1883.84  4970.1 1881.08  4981.1 1877.18  4981.4 1876.68  4985.1 1877.18
  5000.4 1878.19  5013.1 1882.62    5037 1883.35  5048.7 1886.98  5054.1 1889.37
  5081.8 1892.81  5113.9 1900.09  5133.1 1906.31  5162.9 1918.54    5186 1925.96
    5195 1930.27  5224.8 1941.24  5271.8 1956.75  5308.1 1970.97  5320.5 1972.51
#Mann= 5 ,-1 , 0
  4696.2      .1       0  4970.1     .07       0  4981.1     .05       0
  4985.1     .07       0  5048.7      .1       0
Bank Sta=4981.1,4985.1
XS Rating Curve= 0 ,0
Exp/Cntr=0.3,0.1

Type RM Length L Ch R = 1 ,23628   ,412,412,412
BEGIN DESCRIPTION:
Lamb Creek 50.0
END DESCRIPTION:
XS GIS Cut Line= 3
      1896075.03     13882475.03        1896225.       13882625.
      1896374.99     13882774.99
#Sta/Elev= 30
  4782.9 1942.62  4801.2 1938.05  4837.4 1925.62  4841.6  1922.5  4850.1 1918.03
  4870.2 1909.84  4910.5 1891.63  4927.5 1887.52  4944.4 1886.12    4955 1883.05
  4966.9 1877.86  4982.6 1869.09  4997.6 1867.89  4997.8 1867.39  5001.6 1867.89
  5003.8 1869.16  5035.7 1874.22    5059 1879.96  5065.4 1880.91    5076 1880.77
  5086.6 1883.27  5103.5 1889.86    5112 1895.15  5119.4 1902.59  5136.4 1910.13
    5146 1915.77  5169.3 1925.03  5179.9 1928.28    5198 1932.26  5207.1 1933.03
#Mann= 4 ,-1 , 0
  4782.9      .1       0  4966.9     .07       0  4997.6     .05       0
  5001.6      .1       0
Bank Sta=4997.6,5001.6
XS Rating Curve= 0 ,0
Exp/Cntr=0.3,0.1

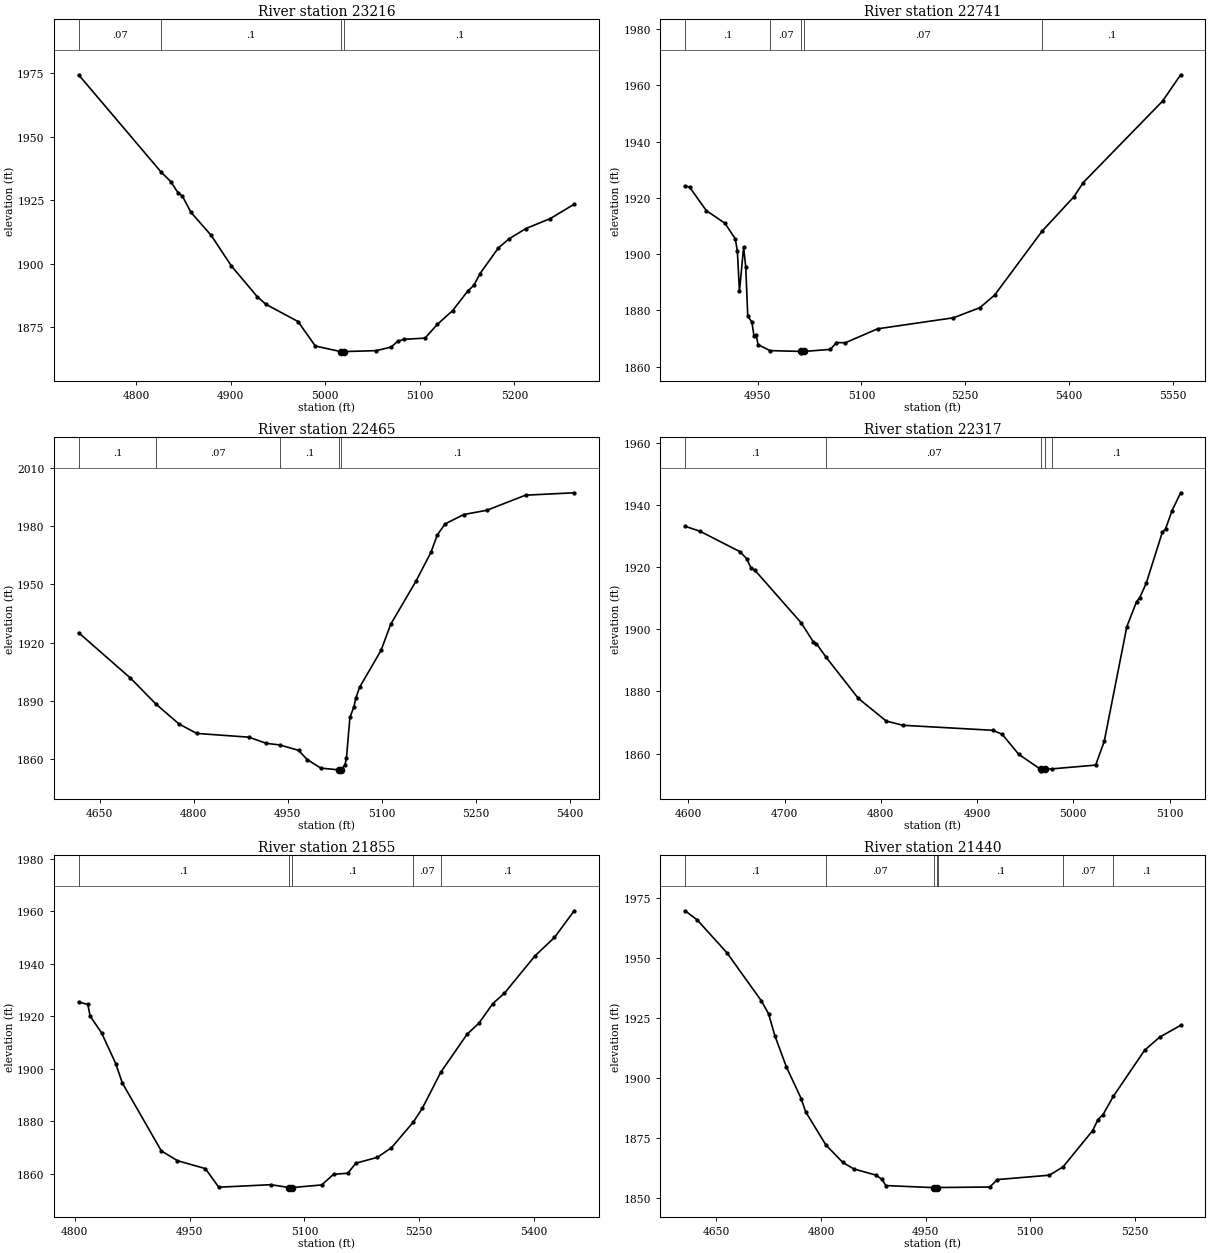
Type RM Length L Ch R = 1 ,23216   ,475,475,475
BEGIN DESCRIPTION:
Lamb Creek 49.0
END DESCRIPTION:
XS GIS Cut Line= 3
      1895774.99       13882925.        1896025.       13882975.
      1896274.98     13882875.01
#Sta/Elev= 30
    4739 1974.42  4826.2 1936.11  4836.4 1932.37    4844 1928.02  4848.7 1926.64
  4857.9 1920.19  4879.3  1911.1  4900.7 1899.05  4928.2 1886.88  4937.4 1883.92
  4971.1 1877.19  4989.4 1867.54  5016.2 1865.36  5016.5 1864.86  5020.2 1865.36
  5053.8 1865.73  5069.4 1867.11  5076.4 1869.36  5082.9 1870.17  5105.5 1870.67
  5118.4 1876.07  5134.6 1881.49  5150.7 1889.25  5157.2 1891.51  5163.6 1896.09
    5183 1906.19  5194.4  1909.8  5212.1 1913.82    5238 1917.77  5263.2 1923.42
#Mann= 4 ,-1 , 0
    4739     .07       0  4826.2      .1       0  5016.2     .05       0
  5020.2      .1       0
Bank Sta=5016.2,5020.2
XS Rating Curve= 0 ,0
Exp/Cntr=0.3,0.1

Type RM Length L Ch R = 1 ,22741   ,276,276,276
BEGIN DESCRIPTION:
Lamb Creek 48.0
END DESCRIPTION:
XS GIS Cut Line= 3
      1896125.01       13883325.        1896275.       13883325.
      1896675.02     13882924.98
#Sta/Elev= 30
  4845.4 1924.18  4851.9 1923.79  4875.9 1915.48  4902.9 1910.96  4917.9  1905.4
  4920.9 1901.02  4923.9 1886.74  4929.9 1902.45    4933 1895.37  4935.9 1877.98
  4941.9 1875.78  4944.9 1870.86  4947.9 1871.24  4950.9 1867.78    4968 1865.68
  5012.9 1865.39  5013.1 1864.89  5016.9 1865.39  5055.2 1866.11    5064 1868.54
  5076.8 1868.47  5123.4 1873.43    5233 1877.35  5271.2 1880.95  5292.4  1885.4
    5361 1908.14    5407 1920.38  5420.4  1925.4    5535 1954.36  5561.1 1963.72
#Mann= 5 ,-1 , 0
  4845.4      .1       0    4968     .07       0  5012.9     .05       0
  5016.9     .07       0    5361      .1       0
Bank Sta=5012.9,5016.9
XS Rating Curve= 0 ,0
Exp/Cntr=0.3,0.1

Type RM Length L Ch R = 1 ,22465   ,148,148,148
BEGIN DESCRIPTION:
Mapping XS 62390ada
END DESCRIPTION:
XS GIS Cut Line= 2
      1896102.64     13883370.26      1896867.84     13883568.22
#Sta/Elev= 30
  4616.4 1925.11  4698.9 1901.78  4739.8 1888.33  4776.4 1878.13  4804.8 1873.24
    4888 1871.31  4915.8 1868.13  4937.8 1867.27  4967.3 1864.51  4980.9 1859.79
  5002.6 1855.38  5031.2 1854.47  5031.5 1853.97  5035.3 1854.47  5041.2 1857.04
  5043.6 1860.62  5049.1 1881.48  5055.3 1886.79  5058.5 1891.41  5064.6 1897.06
  5098.7 1915.96  5114.2 1929.47  5154.3 1951.56  5178.3 1966.47  5188.5 1975.44
  5200.9 1981.14  5230.7 1985.97  5267.7 1988.18  5329.2 1995.93  5406.8 1997.17
#Mann= 5 ,-1 , 0
  4616.4      .1       0  4739.8     .07       0  4937.8      .1       0
  5031.2     .05       0  5035.3      .1       0
Bank Sta=5031.2,5035.3
XS Rating Curve= 0 ,0
Exp/Cntr=0.3,0.1

Type RM Length L Ch R = 1 ,22317   ,462,462,462
BEGIN DESCRIPTION:
Lamb Creek 47.0
END DESCRIPTION:
XS GIS Cut Line= 3
      1896024.99       13883375.        1896375.       13883575.
      1896424.99     13883674.98
#Sta/Elev= 30
  4596.6 1933.09  4612.2 1931.47  4653.7  1924.9  4660.6 1922.64  4665.1 1919.69
  4668.8 1919.06  4717.2 1902.04  4729.7 1895.98  4733.1 1895.33  4743.3 1890.89
  4776.6 1877.73  4805.7 1870.42    4823 1869.08  4916.3 1867.47  4926.1 1866.19
  4943.2 1859.76    4966 1854.93  4966.3 1854.43  4970.1 1854.93  4978.1 1855.07
  5023.2 1856.28  5032.1  1863.9  5055.6 1900.81  5065.7 1908.84    5069 1910.11
  5075.7 1914.73  5092.5 1931.18  5095.8 1932.22  5102.6 1938.15  5111.5 1943.86
#Mann= 5 ,-1 , 0
  4596.6      .1       0  4743.3     .07       0    4966     .05       0
  4970.1     .07       0  4978.1      .1       0
Bank Sta=4966,4970.1
XS Rating Curve= 0 ,0
Exp/Cntr=0.3,0.1

Type RM Length L Ch R = 1 ,21855   ,415,415,415
BEGIN DESCRIPTION:
Lamb Creek 46.0
END DESCRIPTION:
XS GIS Cut Line= 3
        1895975.     13883474.99        1895975.       13883675.
      1896374.98     13883874.99
#Sta/Elev= 30
  4805.1 1925.43  4817.1 1924.46  4820.1 1920.06  4835.1 1913.62  4853.6  1901.9
  4862.1 1894.57  4913.1 1868.66  4934.1 1864.92  4970.6 1861.91  4988.1 1854.81
    5056 1855.77  5080.2 1854.69  5080.5 1854.19  5084.3 1854.69  5122.5 1855.67
  5138.2 1859.76  5156.6 1860.12  5167.2 1863.98  5195.1 1866.17  5213.7 1869.86
  5242.3 1879.67  5253.9 1884.84  5278.2 1898.68  5312.6  1913.2  5327.7 1917.25
  5346.1 1924.81  5361.2 1928.76  5401.5  1943.1  5426.6    1950  5452.3 1960.17
#Mann= 5 ,-1 , 0
  4805.1      .1       0  5080.2     .05       0  5084.3      .1       0
  5242.3     .07       0  5278.2      .1       0
Bank Sta=5080.2,5084.3
XS Rating Curve= 0 ,0
Exp/Cntr=0.3,0.1

Type RM Length L Ch R = 1 ,21440   ,242,242,242
BEGIN DESCRIPTION:
Lamb Creek 45.0
END DESCRIPTION:
XS GIS Cut Line= 3
        1895525.       13883625.        1895775.       13883925.
      1896025.02     13884125.02
#Sta/Elev= 30
  4605.1 1969.53  4622.5 1965.72  4665.1 1952.08  4714.4 1932.15  4724.8 1926.75
  4733.9 1917.56  4750.3 1904.71  4771.6 1891.49    4778 1886.01    4807 1872.24
  4831.3 1864.97  4847.2 1862.25  4878.4 1859.74  4887.1 1858.03    4893 1855.36
  4962.2  1854.5  4962.5    1854  4966.5  1854.5  4968.5 1854.55  5042.2 1854.76
  5052.9 1857.85  5127.6 1859.67  5147.1 1863.11  5189.5 1878.16  5197.3 1882.79
  5204.4  1884.8  5219.2 1892.41  5264.2 1911.61  5285.6    1917  5315.8 1921.95
#Mann= 7 ,-1 , 0
  4605.1      .1       0    4807     .07       0  4962.2     .05       0
  4966.5     .07       0  4968.5      .1       0  5147.1     .07       0
  5219.2      .1       0
Bank Sta=4962.2,4966.5
XS Rating Curve= 0 ,0
Exp/Cntr=0.3,0.1

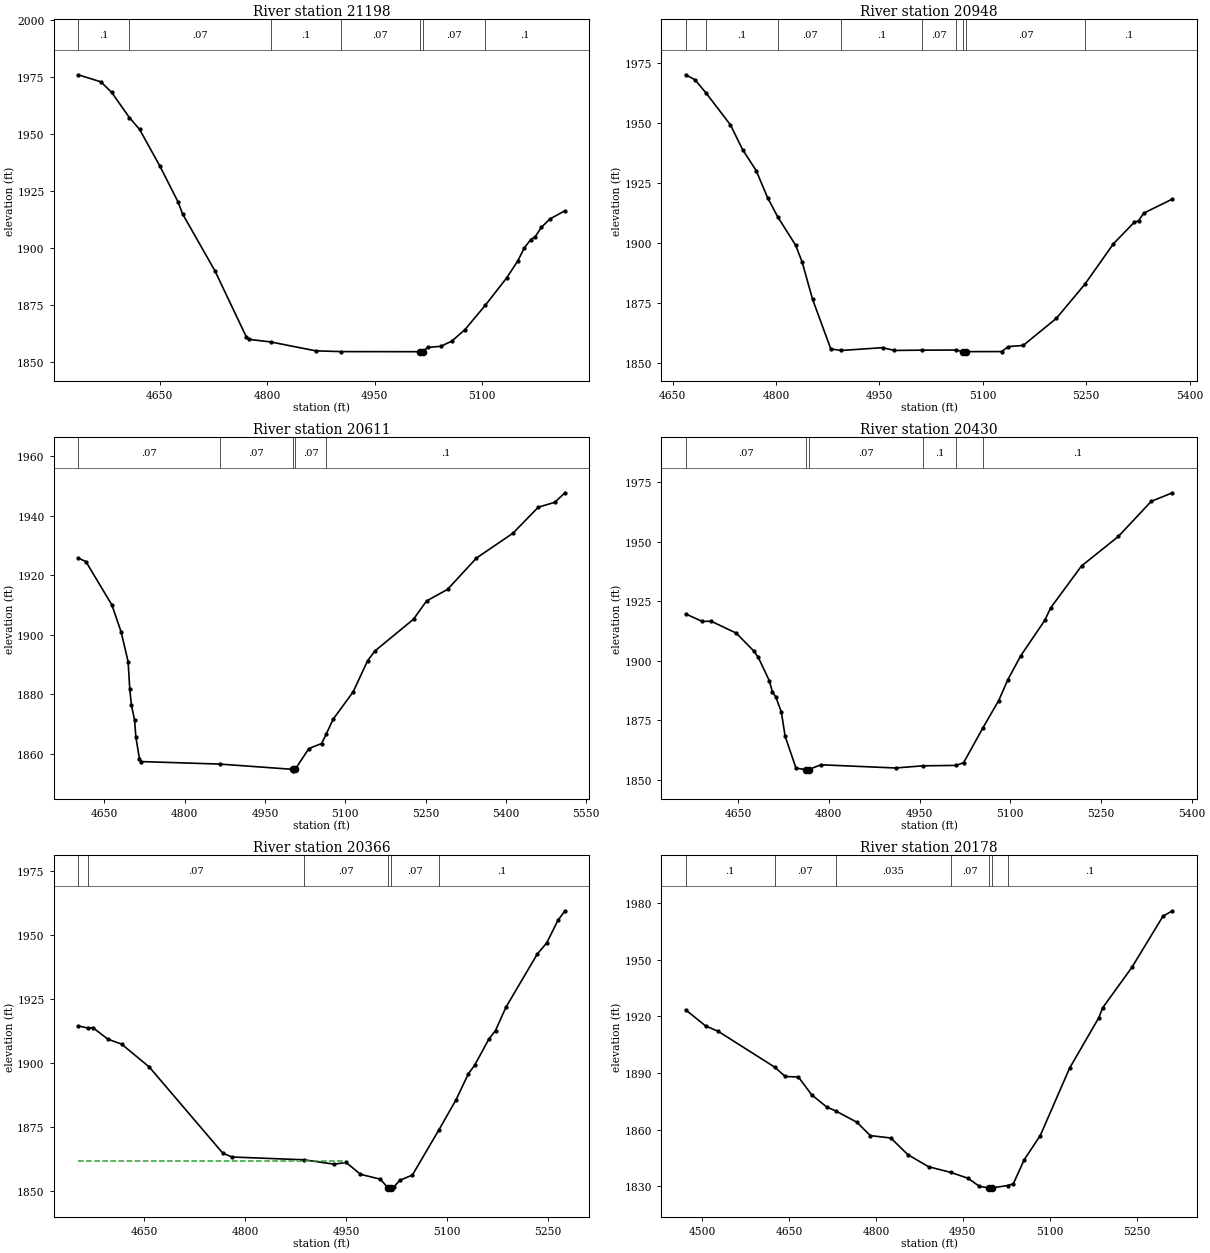
Type RM Length L Ch R = 1 ,21198   ,250,250,250
BEGIN DESCRIPTION:
Mapping XS acd1cd22
END DESCRIPTION:
XS GIS Cut Line= 2
      1895283.88     13884156.72      1895963.53     13884142.77
#Sta/Elev= 30
  4536.2 1976.15  4567.8 1973.06  4582.9 1968.44  4607.7 1957.35  4621.9 1952.18
  4650.3 1936.03  4675.9 1920.15  4681.9 1915.07  4726.9  1890.2  4770.8 1861.17
  4774.9 1859.97    4805 1858.84  4867.9 1854.94  4903.6  1854.6  5012.8 1854.56
  5013.1 1854.06  5017.1 1854.56    5024 1856.42  5042.6 1856.94  5057.9 1859.21
  5076.3 1864.27  5104.5 1874.88  5134.5 1886.96    5150 1894.39    5159 1900.08
    5168 1903.77  5174.4 1905.08    5183 1909.19    5195 1912.86    5216 1916.46
#Mann= 7 ,-1 , 0
  4536.2      .1       0  4607.7     .07       0    4805      .1       0
  4903.6     .07       0  5012.8     .05       0  5017.1     .07       0
  5104.5      .1       0
Bank Sta=5012.8,5017.1
XS Rating Curve= 0 ,0
Exp/Cntr=0.3,0.1

Type RM Length L Ch R = 1 ,20948   ,337,337,337
BEGIN DESCRIPTION:
Lamb Creek 44.0
END DESCRIPTION:
XS GIS Cut Line= 3
      1895324.98     13884224.99      1895628.96     13884337.33
        1895975.       13884175.
#Sta/Elev= 30
    4669 1970.29  4682.7 1968.18  4698.6 1962.69    4734 1949.37  4751.7 1939.02
  4771.4 1930.27  4787.8 1919.04  4802.5 1911.04  4828.5 1899.19    4838 1892.17
  4853.1 1876.63  4879.6 1855.86  4895.1 1855.24  4954.6 1856.41  4971.9 1855.25
  5011.3 1855.37  5061.5 1855.42  5071.8 1854.75  5072.1 1854.25  5076.1 1854.75
  5127.4 1854.78  5137.3 1856.86  5158.7 1857.34  5206.9 1868.66  5248.2 1882.88
  5289.7  1899.8  5319.6 1908.65  5326.2 1909.39  5333.6 1912.56  5375.3 1918.44
#Mann= 9 ,-1 , 0
    4669     .07       0  4698.6      .1       0  4802.5     .07       0
  4895.1      .1       0  5011.3     .07       0  5061.5     .07       0
  5071.8     .05       0  5076.1     .07       0  5248.2      .1       0
Bank Sta=5071.8,5076.1
XS Rating Curve= 0 ,0
Exp/Cntr=0.3,0.1

Type RM Length L Ch R = 1 ,20611   ,181,181,181
BEGIN DESCRIPTION:
Lamb Creek 43.0
END DESCRIPTION:
XS GIS Cut Line= 3
      1895475.02       13884575.        1895875.       13884525.
       1896322.7     13884288.76
#Sta/Elev= 30
  4601.2 1925.76  4615.6 1924.59  4664.2 1910.01  4681.2 1901.09  4694.4 1891.05
  4697.5  1881.9  4700.5 1876.54  4706.5 1871.44  4708.9 1865.75  4715.6 1858.43
  4718.6  1857.5  4865.4 1856.66  5002.1 1854.89  5002.4 1854.39  5006.4 1854.89
  5032.1 1861.88  5055.8 1863.55  5064.2 1866.61  5077.3 1871.69  5114.6 1880.83
  5141.7 1891.31  5155.3 1894.58  5227.5 1905.26  5251.9 1911.39    5291 1915.25
    5345 1925.77  5413.1 1934.09  5460.6 1942.83  5491.1 1944.46  5510.5 1947.67
#Mann= 5 ,-1 , 0
  4601.2     .07       0  4865.4     .07       0  5002.1     .05       0
  5006.4     .07       0  5064.2      .1       0
Bank Sta=5002.1,5006.4
XS Rating Curve= 0 ,0
Exp/Cntr=0.3,0.1

Type RM Length L Ch R = 1 ,20430   ,64,64,64
BEGIN DESCRIPTION:
Mapping XS fb3e03d8
END DESCRIPTION:
XS GIS Cut Line= 2
      1895444.48     13884632.55      1896237.76     13884768.25
#Sta/Elev= 30
  4563.4 1919.66  4590.9 1916.49  4605.4 1916.61    4647 1911.61  4676.1 1904.08
  4683.4 1901.46  4701.6  1891.7  4706.8 1887.03  4712.6 1884.72  4721.7  1878.4
  4727.8 1868.37  4745.8 1854.99  4762.1 1854.33  4762.4 1853.83  4766.5 1854.33
  4786.9 1856.37  4910.4 1855.03  4955.2 1855.93    5011 1856.11    5023  1857.3
  5054.7 1871.81  5080.9 1883.31  5096.1 1892.09  5117.4 1902.12    5157 1916.93
  5166.8 1922.18  5217.8 1939.76  5278.7 1952.14  5333.1 1966.88  5368.2 1970.47
#Mann= 6 ,-1 , 0
  4563.4     .07       0  4762.1     .05       0  4766.5     .07       0
  4955.2      .1       0    5011    .035       0  5054.7      .1       0
Bank Sta=4762.1,4766.5
XS Rating Curve= 0 ,0
Exp/Cntr=0.3,0.1

Type RM Length L Ch R = 1 ,20366   ,188,188,188
BEGIN DESCRIPTION:
Lambs Creek 42.1
END DESCRIPTION:
XS GIS Cut Line= 4
      1895423.73     13884678.33      1895624.29     13884787.73
      1895832.62     13884756.48      1896108.69      13884826.8
#Sta/Elev= 30
  4551.6 1914.49  4566.6 1913.61  4573.3 1913.82  4595.8 1909.32  4616.3 1907.36
  4657.3 1898.47  4766.7 1864.89  4780.3 1863.42  4886.7 1862.34  4932.2 1860.63
  4950.2 1861.28  4971.4 1856.67  5000.9 1854.79  5011.9 1851.52  5012.2 1851.02
  5016.3 1851.52  5020.6 1851.66  5029.8 1854.32  5048.6  1856.4  5087.7 1873.83
  5113.4 1885.65    5132 1895.89  5141.3  1899.2  5162.1 1909.25  5172.2 1912.67
  5187.7 1921.75  5234.2 1942.41  5248.5 1946.87  5265.1 1955.63  5275.6 1959.32
#Mann= 6 ,-1 , 0
  4551.6      .1       0  4566.6     .07       0  4886.7     .07       0
  5011.9     .05       0  5016.3     .07       0  5087.7      .1       0
#XS Ineff= 2 , 0
         4947.55  1861.8
Permanent Ineff=
       F       F
Bank Sta=5011.9,5016.3
XS Rating Curve= 0 ,0
Exp/Cntr=0.3,0.1

Type RM Length L Ch R = 1 ,20178   ,422,422,422
BEGIN DESCRIPTION:
Lamb Creek 42.0
END DESCRIPTION:
XS GIS Cut Line= 3
       1895292.1     13884722.25        1895775.       13884925.
      1896075.03     13885025.01
#Sta/Elev= 30
  4471.7 1923.43  4506.2 1914.92  4527.8 1912.08  4625.4 1893.11  4643.5 1888.19
  4666.3  1887.9  4689.1 1878.51  4715.1 1872.03  4730.8 1869.93  4767.2 1863.96
  4790.4 1856.89  4825.7 1855.64    4855 1846.84  4890.8 1840.42    4929 1837.45
  4959.1  1834.3  4978.7 1830.01  4995.9 1829.23  4996.2 1828.73  5000.3 1829.23
  5027.1 1830.48    5037 1831.34  5055.9 1844.16  5083.5 1856.88  5134.1 1892.53
  5184.7 1919.34  5191.1 1924.45  5241.6  1945.9  5295.4 1973.02  5311.7 1975.85
#Mann= 7 ,-1 , 0
  4471.7      .1       0  4625.4     .07       0  4730.8    .035       0
    4929     .07       0  4995.9     .05       0  5000.3     .07       0
  5027.1      .1       0
Bank Sta=4995.9,5000.3
XS Rating Curve= 0 ,0
Exp/Cntr=0.3,0.1

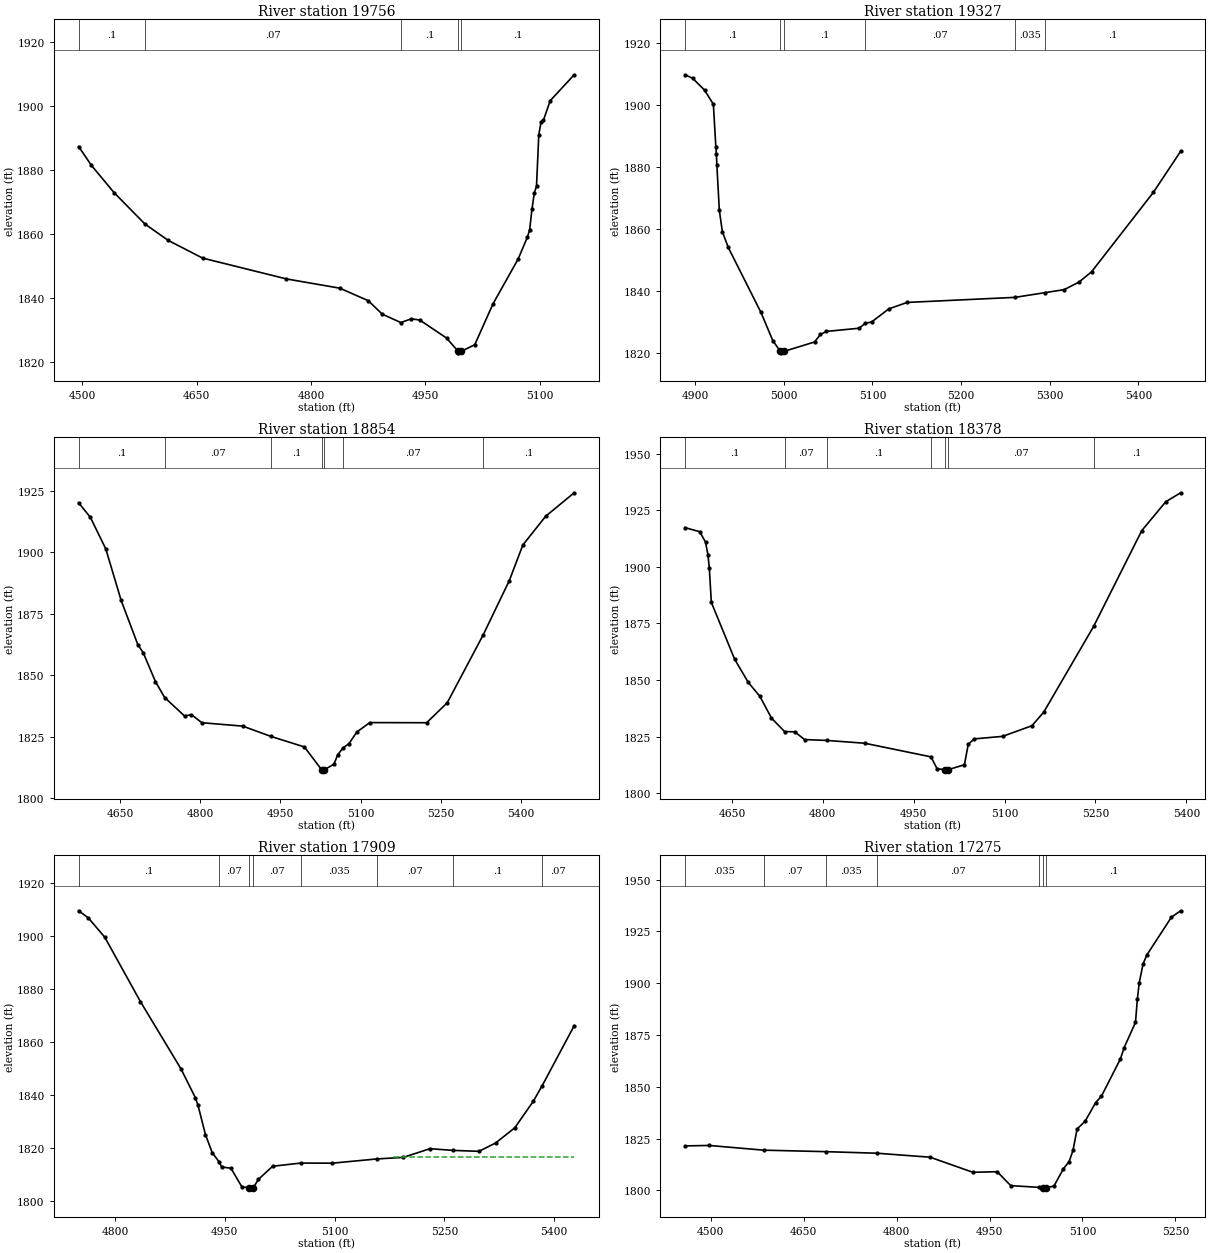
Type RM Length L Ch R = 1 ,19756   ,429,429,429
BEGIN DESCRIPTION:
Lamb Creek 41.0
END DESCRIPTION:
XS GIS Cut Line= 3
      1895274.98     13884874.97        1895575.       13885275.
      1895724.96       13885275.
#Sta/Elev= 30
  4495.2 1887.32    4512  1881.4    4542 1872.81  4582.2 1863.06  4612.7 1857.94
  4657.7 1852.41  4767.8 1845.88  4837.7 1842.99  4875.2 1839.06  4893.5 1834.85
  4917.9 1832.22  4931.5  1833.4  4942.7 1833.01  4977.8 1827.37    4993 1823.25
  4993.3 1822.75  4997.4 1823.25  5014.8 1825.29  5038.8 1838.11  5071.8 1852.15
  5083.8 1858.95  5086.8 1861.22  5089.8 1867.63  5092.8 1872.66  5095.8 1874.95
  5098.8 1891.07  5101.8 1895.04  5104.8 1895.49  5113.8 1901.67  5145.2 1909.77
#Mann= 5 ,-1 , 0
  4495.2      .1       0  4582.2     .07       0  4917.9      .1       0
    4993     .05       0  4997.4      .1       0
Bank Sta=4993,4997.4
XS Rating Curve= 0 ,0
Exp/Cntr=0.3,0.1

Type RM Length L Ch R = 1 ,19327   ,473,473,473
BEGIN DESCRIPTION:
Lamb Creek 40.0
END DESCRIPTION:
XS GIS Cut Line= 3
      1895274.99     13885675.01        1895375.       13885625.
      1895774.97     13885425.01
#Sta/Elev= 30
  4888.7 1909.88  4897.1 1908.77  4910.6 1904.95  4920.6 1900.37  4923.4 1886.52
    4924 1884.37  4924.5 1880.91  4927.3 1866.23  4930.7 1859.31  4937.4 1854.17
  4974.3 1833.21  4987.7  1824.1  4996.1 1820.69  4996.4 1820.19  5000.6 1820.69
  5034.7 1823.69  5041.4 1826.12  5048.1  1827.1    5085 1828.13  5092.1 1829.73
    5099 1830.12  5118.5 1834.37  5139.2 1836.45  5260.6 1838.08  5295.1 1839.62
  5316.4 1840.58  5333.2 1843.04  5347.2 1846.32    5417 1871.98  5447.7 1885.19
#Mann= 6 ,-1 , 0
  4888.7      .1       0  4996.1     .05       0  5000.6      .1       0
  5092.1     .07       0  5260.6    .035       0  5295.1      .1       0
Bank Sta=4996.1,5000.6
XS Rating Curve= 0 ,0
Exp/Cntr=0.3,0.1

Type RM Length L Ch R = 1 ,18854   ,476,476,476
BEGIN DESCRIPTION:
Lamb Creek 39.0
END DESCRIPTION:
XS GIS Cut Line= 3
      1895174.99       13885875.        1895575.       13886025.
      1895874.99     13886424.99
#Sta/Elev= 30
  4572.6  1920.1  4594.5  1914.2  4623.4 1901.36  4652.2 1880.37  4683.6 1862.29
  4693.4 1859.18  4716.3  1847.4  4733.6  1840.9  4770.8  1833.4  4783.6 1833.96
  4803.2 1830.67  4879.7 1829.28  4932.8 1825.07    4995 1820.82  5027.1  1811.6
  5027.5  1811.1  5032.5  1811.6  5050.2 1813.75  5057.4 1817.63  5067.3 1820.42
  5078.5 1822.16    5093 1826.86  5117.4 1830.72  5223.8 1830.66  5262.3 1838.79
  5329.2 1866.23  5378.5 1888.48  5403.8 1902.96  5446.6 1914.64  5499.8 1924.17
#Mann= 7 ,-1 , 0
  4572.6      .1       0  4733.6     .07       0  4932.8      .1       0
  5027.1     .05       0  5032.5      .1       0  5067.3     .07       0
  5329.2      .1       0
Bank Sta=5027.1,5032.5
XS Rating Curve= 0 ,0
Exp/Cntr=0.3,0.1

Type RM Length L Ch R = 1 ,18378   ,469,469,469
BEGIN DESCRIPTION:
Lamb Creek 38.0
END DESCRIPTION:
XS GIS Cut Line= 3
      1894975.01       13886275.        1895375.       13886425.
        1895675.       13886675.
#Sta/Elev= 30
  4572.8  1917.3  4596.9 1915.52  4606.5  1910.9  4610.5 1905.36  4612.8 1899.35
  4616.1 1884.28  4654.5  1859.2    4677 1848.92  4696.2 1842.77  4715.3 1833.15
  4736.9  1827.2  4753.9 1827.06  4769.9 1823.65  4807.6 1823.25  4869.2 1822.03
  4978.5 1816.01  4988.5  1810.8  5001.2 1810.33  5001.6 1809.83  5006.7 1810.33
  5033.7 1812.53  5040.1  1821.6  5049.9 1823.95  5096.8 1825.07  5145.2 1829.78
  5164.7 1835.81  5246.9 1873.65  5326.4 1916.01    5366 1928.77  5390.5 1932.72
#Mann= 7 ,-1 , 0
  4572.8      .1       0  4736.9     .07       0  4807.6      .1       0
  4978.5     .07       0  5001.2     .05       0  5006.7     .07       0
  5246.9      .1       0
Bank Sta=5001.2,5006.7
XS Rating Curve= 0 ,0
Exp/Cntr=0.3,0.1

Type RM Length L Ch R = 1 ,17909   ,634,634,634
BEGIN DESCRIPTION:
Lamb Creek 37.0
END DESCRIPTION:
XS GIS Cut Line= 3
      1894824.98     13886574.98        1895025.       13886725.
      1895424.97     13886874.99
#Sta/Elev= 30
  4750.2 1909.59  4763.4 1906.91  4785.9 1899.61  4834.7 1875.23  4889.9 1849.92
  4909.7 1838.95  4913.4 1836.01  4923.5    1825  4932.7  1818.2  4941.9 1814.78
  4945.6 1812.77  4958.4 1812.27  4973.4 1805.18  4983.6 1804.99    4984 1804.49
  4989.1 1804.99  4995.9 1808.09  5015.4 1813.03  5053.8 1814.23  5096.9 1814.19
  5157.8 1815.79  5193.8 1816.38  5230.4 1819.67  5261.8 1819.02  5297.3 1818.67
  5320.1 1821.83  5346.3 1827.58  5371.4 1837.54  5383.5 1843.39  5427.4 1866.13
#Mann= 8 ,-1 , 0
  4750.2      .1       0  4941.9     .07       0  4983.6     .05       0
  4989.1     .07       0  5053.8    .035       0  5157.8     .07       0
  5261.8      .1       0  5383.5     .07       0
#XS Ineff= 2 , 0
                         5180.85         1816.57
Permanent Ineff=
       F       F
Bank Sta=4983.6,4989.1
XS Rating Curve= 0 ,0
Exp/Cntr=0.3,0.1

Type RM Length L Ch R = 1 ,17275   ,281,281,281
BEGIN DESCRIPTION:
Lamb Creek 36.0
END DESCRIPTION:
XS GIS Cut Line= 4
      1894749.69      13886986.9      1894964.17      13887078.1
      1895223.46     13887084.92      1895525.02       13887025.
#Sta/Elev= 30
  4458.6 1821.47  4497.4 1821.69  4585.2 1819.42  4685.6  1818.7  4768.7 1817.93
  4854.1 1816.02  4923.1 1808.74  4962.3 1809.02  4984.2 1802.31  5030.5 1801.45
  5036.1 1801.25  5036.5 1800.75  5041.6 1801.25  5054.1 1802.14  5069.4  1810.5
  5078.5 1813.91  5084.7 1819.27  5091.4 1829.69  5104.2 1833.31  5121.4 1842.41
  5130.6 1845.43  5161.2 1863.39  5167.3 1868.92  5185.6 1881.06  5188.7 1892.55
  5191.7 1900.23  5197.9 1909.38    5204 1913.65  5243.7 1931.89  5258.5 1934.95
#Mann= 7 ,-1 , 0
  4458.6    .035       0  4585.2     .07       0  4685.6    .035       0
  4768.7     .07       0  5030.5      .1       0  5036.1     .05       0
  5041.6      .1       0
Bank Sta=5036.1,5041.6
XS Rating Curve= 0 ,0
Exp/Cntr=0.3,0.1