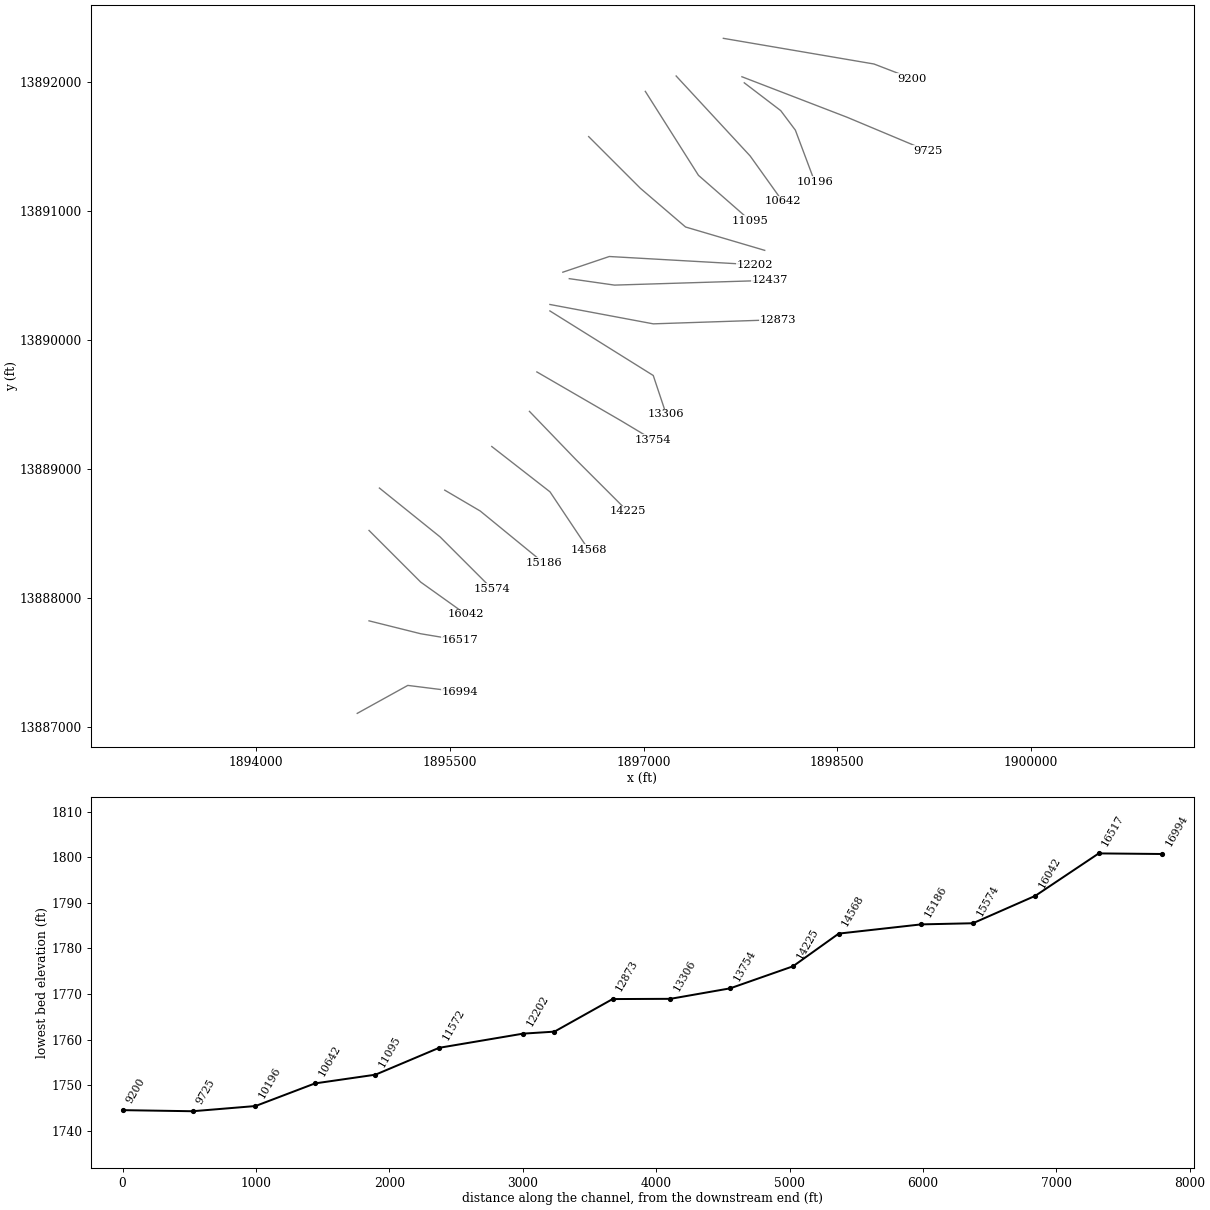
HEC-RAS study Lambs Creek.prj: Lambs Creek Base Level Engineering

--- Lambs Creek.g01 (geometry) --- (continued)

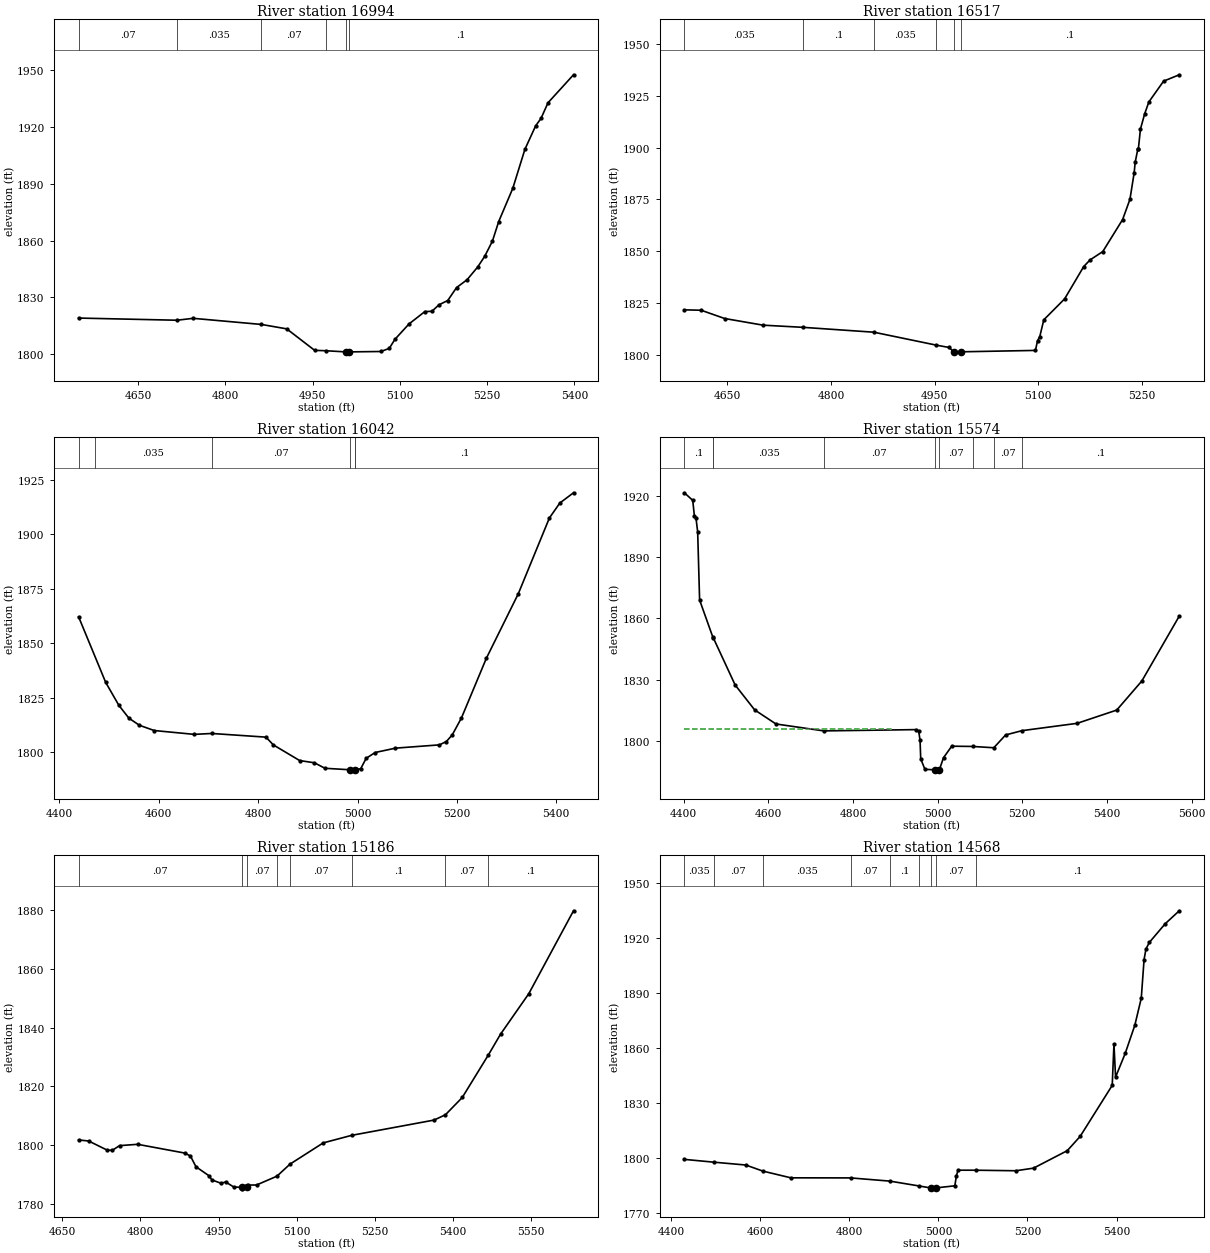
Type RM Length L Ch R = 1 ,16994   ,477,477,477
BEGIN DESCRIPTION:
Lamb Creek 35.0
END DESCRIPTION:
XS GIS Cut Line= 3
      1894783.68     13887108.39        1895175.       13887325.
      1895575.01       13887275.
#Sta/Elev= 30
  4547.9 1819.08  4716.9 1817.93  4744.7 1818.94  4862.1  1815.7  4905.5 1813.37
  4953.5 1802.01  4972.8  1801.8  5007.1 1801.19  5007.5 1800.69  5012.6 1801.19
  5067.3  1801.4  5081.7 1803.04  5091.5 1807.85  5115.6 1815.95  5142.9 1822.51
    5155 1822.64    5167 1826.07  5182.2 1828.36  5197.3 1835.18  5215.4 1839.34
  5233.6 1846.06  5245.7 1851.71    5259 1859.79  5269.8 1870.13    5294  1887.7
  5314.8 1908.31  5333.3 1920.76  5342.4 1924.61  5354.5 1932.92  5398.3 1947.72
#Mann= 6 ,-1 , 0
  4547.9     .07       0  4716.9    .035       0  4862.1     .07       0
  4972.8      .1       0  5007.1     .05       0  5012.6      .1       0
Bank Sta=5007.1,5012.6
XS Rating Curve= 0 ,0
Exp/Cntr=0.3,0.1

Type RM Length L Ch R = 1 ,16517   ,475,475,475
BEGIN DESCRIPTION:
Lamb Creek 34.0
END DESCRIPTION:
XS GIS Cut Line= 3
        1894875.       13887825.        1895275.       13887725.
      1895574.95     13887675.01
#Sta/Elev= 30
  4587.7  1821.6    4612  1821.4    4646 1817.41  4701.6 1814.19  4759.6 1813.14
    4862 1810.79  4951.9 1804.57  4970.7 1803.43  4977.7 1801.32  4978.2 1800.82
  4988.4 1801.32  5095.9 1801.99  5098.9 1806.65  5102.2 1808.69    5108 1816.78
  5138.1 1826.88  5165.8 1842.51  5174.9  1845.7  5193.4 1849.76  5222.1 1865.23
  5232.7    1875  5238.8 1887.81  5240.3 1892.96    5244 1899.09  5244.9 1899.37
  5247.9 1908.92    5254 1916.29  5260.1 1922.06  5281.4 1932.09  5304.1 1935.17
#Mann= 6 ,-1 , 0
  4587.7    .035       0  4759.6      .1       0    4862    .035       0
  4951.9      .1       0  4977.7     .05       0  4988.4      .1       0
Bank Sta=4977.7,4988.4
XS Rating Curve= 0 ,0
Exp/Cntr=0.3,0.1

Type RM Length L Ch R = 1 ,16042   ,468,468,468
BEGIN DESCRIPTION:
Lamb Creek 33.0
END DESCRIPTION:
XS GIS Cut Line= 3
        1894875.       13888525.        1895275.       13888125.
      1895624.99       13887875.
#Sta/Elev= 30
  4438.8  1862.1  4493.3 1832.06  4519.8 1821.55    4540 1815.66  4561.2  1812.4
  4590.9    1810  4671.5 1808.24  4706.9 1808.65  4815.8 1806.97  4830.6 1803.42
  4883.6 1796.24  4913.3 1795.22  4934.5  1792.7  4984.3 1792.03  4984.8 1791.53
    4995 1792.03  4995.4 1792.07  5006.4 1792.49  5017.4 1797.26  5035.5 1799.93
  5076.4 1801.93  5164.9 1803.43  5178.8 1804.97  5190.7 1808.02  5209.2  1815.8
  5259.4 1843.18  5323.4 1872.61  5386.1 1907.39  5407.1 1914.23  5434.6 1918.93
#Mann= 6 ,-1 , 0
  4438.8     .07       0  4471.3    .035       0  4706.9     .07       0
  4984.3     .05       0    4995     .07       0  4995.4      .1       0
Bank Sta=4984.3,4995
XS Rating Curve= 0 ,0
Exp/Cntr=0.3,0.1

Type RM Length L Ch R = 1 ,15574   ,388,388,388
BEGIN DESCRIPTION:
Lamb Creek 32.0
END DESCRIPTION:
XS GIS Cut Line= 3
      1894955.32     13888853.35        1895425.       13888475.
        1895825.       13888075.
#Sta/Elev= 30
    4402 1921.34  4421.8 1917.63  4425.7 1909.91  4429.4 1909.08  4433.4  1902.3
    4438 1868.95  4468.7 1851.13  4470.7 1850.31    4522 1827.42    4568 1815.28
  4618.3  1808.4  4731.3 1805.02  4949.6 1805.65  4955.4 1804.91  4958.6 1800.48
  4960.2 1791.37  4970.1 1786.25  4993.4 1786.01  4993.9 1785.51  5004.2 1786.01
    5014 1791.92  5033.4 1797.55  5082.9 1797.42  5132.8 1796.79  5160.7 1803.04
  5199.4 1805.14  5329.7 1808.72  5423.1 1815.19  5482.5 1829.43  5570.8  1861.1
#Mann= 9 ,-1 , 0
    4402      .1       0  4468.7     .07       0  4470.7    .035       0
  4731.3     .07       0  4993.4     .05       0  5004.2     .07       0
  5082.9      .1       0  5132.8     .07       0  5199.4      .1       0
#XS Ineff= 2 , 0
         4890.31 1805.87
Permanent Ineff=
       F       F
Bank Sta=4993.4,5004.2
XS Rating Curve= 0 ,0
Exp/Cntr=0.3,0.1

Type RM Length L Ch R = 1 ,15186   ,618,618,618
BEGIN DESCRIPTION:
Lamb Creek 31.0
END DESCRIPTION:
XS GIS Cut Line= 3
      1895460.92     13888837.13      1895735.64     13888675.53
        1896225.       13888275.
#Sta/Elev= 30
  4681.1 1801.85  4700.5 1801.49  4736.2 1798.38  4745.9 1798.33  4759.8 1799.92
  4794.6 1800.37  4885.1  1797.4    4896  1796.4  4906.7 1792.75  4931.5 1789.72
  4937.3 1788.29  4955.1 1787.13  4963.6  1787.6  4979.1  1785.9  4994.3 1785.76
  4994.8 1785.26  5005.3 1785.76  5007.3 1786.53  5023.2 1786.57  5062.3 1789.56
  5087.4 1793.65  5151.2 1800.85    5206 1803.42  5364.1 1808.59  5386.1  1810.4
  5418.4 1816.26  5468.8 1830.75    5492 1837.75  5546.3 1851.49  5632.2 1879.62
#Mann= 8 ,-1 , 0
  4681.1     .07       0  4994.3     .05       0  5005.3     .07       0
  5062.3      .1       0  5087.4     .07       0    5206      .1       0
  5386.1     .07       0  5468.8      .1       0
Bank Sta=4994.3,5005.3
XS Rating Curve= 0 ,0
Exp/Cntr=0.3,0.1

Type RM Length L Ch R = 1 ,14568   ,343,343,343
BEGIN DESCRIPTION:
Lamb Creek 30.0
END DESCRIPTION:
XS GIS Cut Line= 3
        1895825.       13889175.      1896275.82     13888823.85
      1896575.02     13888374.97
#Sta/Elev= 30
  4429.8 1799.31  4495.5 1797.79  4567.7 1796.23  4605.9 1792.92  4668.7 1789.25
    4803  1789.2  4891.1 1787.45  4956.8  1784.8  4982.4 1783.74  4982.9 1783.24
  4993.8 1783.74  5036.9 1784.89  5040.5 1790.39  5044.1 1793.41  5083.6  1793.4
    5174  1793.1  5213.6 1794.53  5289.3 1804.06  5318.1  1811.8  5390.2 1839.68
  5394.1 1862.26  5397.7 1844.16  5419.3 1857.08  5440.9 1872.43  5455.4 1887.22
  5461.7 1908.31  5465.9 1914.02  5473.4  1917.6  5509.2 1927.84  5540.7 1934.89
#Mann= 9 ,-1 , 0
  4429.8    .035       0  4495.5     .07       0  4605.9    .035       0
    4803     .07       0  4891.1      .1       0  4956.8     .07       0
  4982.4     .05       0  4993.8     .07       0  5083.6      .1       0
Bank Sta=4982.4,4993.8
XS Rating Curve= 0 ,0
Exp/Cntr=0.3,0.1

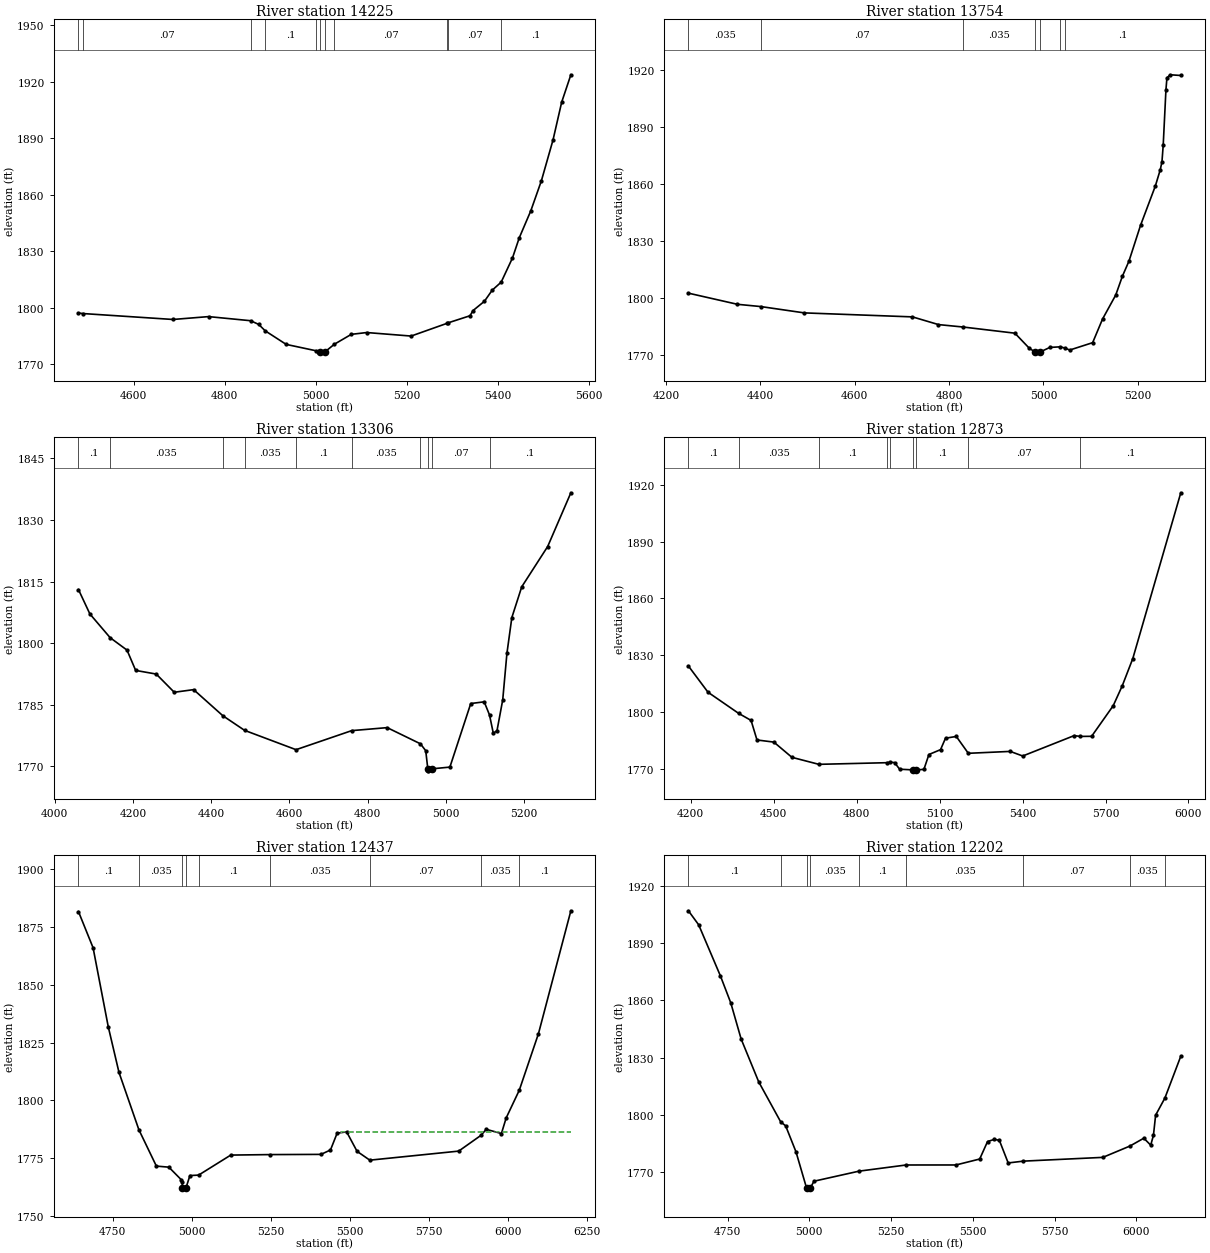
Type RM Length L Ch R = 1 ,14225   ,471,471,471
BEGIN DESCRIPTION:
Lamb Creek 29.0
END DESCRIPTION:
XS GIS Cut Line= 3
      1896116.71     13889447.16        1896475.       13889075.
      1896875.01     13888674.99
#Sta/Elev= 30
  4478.6 1797.18  4488.7 1796.93  4686.3 1793.79  4764.5 1795.31  4856.9 1793.13
  4874.7 1791.18  4889.1 1787.75  4935.2 1780.55  5000.6 1777.18  5008.9 1776.57
  5009.4 1776.07  5020.3 1776.57    5041 1780.63  5078.3 1785.89  5112.2 1786.85
  5209.8 1784.98  5288.6 1791.73  5291.7 1792.05  5339.3 1795.77  5345.6 1798.46
    5371 1803.48    5388 1809.34  5407.7  1813.6  5432.6 1826.47  5447.4 1837.11
  5472.9 1851.52  5496.2 1867.51  5521.7 1889.14  5540.7 1909.18  5560.9 1923.73
#Mann= 11 ,-1 , 0
  4478.6    .035       0  4488.7     .07       0  4856.9    .035       0
  4889.1      .1       0  5000.6    .035       0  5008.9     .05       0
  5020.3    .035       0    5041     .07       0  5288.6    .035       0
  5291.7     .07       0  5407.7      .1       0
Bank Sta=5008.9,5020.3
XS Rating Curve= 0 ,0
Exp/Cntr=0.3,0.1

Type RM Length L Ch R = 1 ,13754   ,448,448,448
BEGIN DESCRIPTION:
Lamb Creek 28.0
END DESCRIPTION:
XS GIS Cut Line= 3
      1896174.13     13889752.59        1896825.       13889375.
      1897074.99     13889225.01
#Sta/Elev= 30
  4247.3 1802.63  4351.2 1796.77  4400.7 1795.58  4493.1 1792.25  4722.4 1790.15
  4777.5  1786.1  4830.4  1784.8  4939.5 1781.58  4970.2 1773.62    4982 1771.74
  4982.5 1771.24  4993.5 1771.74  5013.5 1774.08  5035.2  1774.4  5045.4 1773.78
  5055.8 1772.71  5104.4 1776.59  5125.4 1789.02  5153.4 1801.67  5167.4 1811.49
  5181.4 1819.48  5205.9 1838.27  5237.4 1859.03  5247.9 1867.66  5251.4 1871.84
    5254 1880.41  5259.8 1909.56  5261.9 1915.86  5268.9 1917.49  5291.3 1917.12
#Mann= 7 ,-1 , 0
  4247.3    .035       0  4400.7     .07       0  4830.4    .035       0
    4982     .05       0  4993.5    .035       0  5035.2     .07       0
  5045.4      .1       0
Bank Sta=4982,4993.5
XS Rating Curve= 0 ,0
Exp/Cntr=0.3,0.1

Type RM Length L Ch R = 1 ,13306   ,433,433,433
BEGIN DESCRIPTION:
Lamb Creek 27.0
END DESCRIPTION:
XS GIS Cut Line= 3
      1896274.96     13890225.03        1897075.       13889725.
      1897175.01     13889424.98
#Sta/Elev= 30
  4060.5 1813.07  4089.7 1807.14  4141.5 1801.36  4184.7 1798.33  4206.8 1793.39
  4259.5  1792.5  4305.5 1788.07  4355.1 1788.71  4429.8 1782.36  4485.4  1778.8
  4617.1 1774.09  4759.6 1778.73  4850.3 1779.46  4935.4 1775.52  4948.9 1773.84
  4954.2 1769.44  4954.7 1768.94  4965.9 1769.44  5010.7 1769.85  5064.1 1785.33
  5098.5 1785.74  5112.1 1782.54  5121.8 1778.08  5131.3 1778.75  5145.9 1786.24
  5156.6 1797.53  5169.2 1806.26  5194.5 1813.74  5260.9 1823.56  5320.2 1836.64
#Mann= 10 ,-1 , 0
  4060.5      .1       0  4141.5    .035       0  4429.8     .07       0
  4485.4    .035       0  4617.1      .1       0  4759.6    .035       0
  4935.4     .07       0  4954.2     .05       0  4965.9     .07       0
  5112.1      .1       0
Bank Sta=4954.2,4965.9
XS Rating Curve= 0 ,0
Exp/Cntr=0.3,0.1

Type RM Length L Ch R = 1 ,12873   ,436,436,436
BEGIN DESCRIPTION:
Lamb Creek 26.0
END DESCRIPTION:
XS GIS Cut Line= 3
      1896275.04     13890274.99        1897075.       13890125.
      1898041.06     13890157.18
#Sta/Elev= 30
  4191.7  1824.3  4262.6 1810.43  4373.2 1799.28  4418.3 1795.54  4439.7  1785.2
  4500.7 1784.08    4566 1776.03  4663.4 1772.33  4908.9 1773.19  4921.3 1773.43
  4937.2 1773.26  4955.5 1769.75  5004.5 1769.39    5005 1768.89  5016.2 1769.39
  5043.3 1769.67  5061.4 1777.52  5103.4 1780.09  5121.4 1786.14  5160.4 1787.06
  5203.9 1778.16  5355.5 1779.16  5400.6 1776.73  5586.7 1787.51    5609 1787.08
  5649.7 1787.14  5727.8 1803.31  5760.7  1813.9  5798.6 1828.22  5972.2 1915.85
#Mann= 9 ,-1 , 0
  4191.7      .1       0  4373.2    .035       0  4663.4      .1       0
  4908.9    .035       0  4921.3      .1       0  5004.5     .05       0
  5016.2      .1       0  5203.9     .07       0    5609      .1       0
#XS Ineff= 2 , 0
                         5140.86         1784.91
Permanent Ineff=
       F       F
Bank Sta=5004.5,5016.2
XS Rating Curve= 0 ,0
Exp/Cntr=0.3,0.1

Type RM Length L Ch R = 1 ,12437   ,235,235,235
BEGIN DESCRIPTION:
Lamb Creek 25.0
END DESCRIPTION:
XS GIS Cut Line= 3
      1896425.04     13890474.99        1896775.       13890425.
      1897977.12       13890462.
#Sta/Elev= 30
  4642.3 1881.74  4688.5 1866.07  4736.4 1831.92  4770.3 1812.16  4833.3  1787.3
  4888.5 1771.59  4927.9 1771.13  4967.3 1765.68  4970.3 1764.74  4970.5 1762.25
    4971 1761.75  4982.3 1762.25  4994.5  1767.5    5022 1767.69  5123.6 1776.36
  5247.4 1776.57  5408.8 1776.66  5438.8 1778.58  5459.8 1785.84  5489.8 1786.42
  5522.8 1777.98  5563.1 1774.16    5844 1778.08  5914.7 1784.93    5931 1787.52
    5979 1785.68    5994 1792.42  6035.5 1804.44  6096.1 1828.91  6198.5 1882.09
#Mann= 9 ,-1 , 0
  4642.3      .1       0  4833.3    .035       0  4970.5    .035       0
  4982.3    .035       0    5022      .1       0  5247.4    .035       0
  5563.1     .07       0  5914.7    .035       0  6035.5      .1       0
#XS Ineff= 2 , 0
                         5472.73         1786.27
Permanent Ineff=
       F       F
Bank Sta=4970.5,4982.3
XS Rating Curve= 0 ,0
Exp/Cntr=0.3,0.1

Type RM Length L Ch R = 1 ,12202   ,630,630,630
BEGIN DESCRIPTION:
Lamb Creek 24.0
END DESCRIPTION:
XS GIS Cut Line= 3
      1896375.05     13890525.02      1896734.84     13890646.52
      1897858.58     13890582.76
#Sta/Elev= 30
  4630.4 1906.93  4661.8 1899.58  4728.2 1872.85  4759.9 1858.72  4791.6 1839.78
  4845.4 1817.31  4912.6 1796.37  4927.7  1794.3  4959.3 1780.69  4991.5 1761.81
    4992 1761.31  5003.3 1761.81  5014.2  1765.3    5152 1770.57  5295.9  1773.8
  5448.3 1773.81  5520.9 1776.92  5544.9 1786.08    5566 1787.23    5581 1786.72
    5608 1774.87  5654.7 1775.82  5897.4 1777.79  5980.2 1783.72  6022.7 1787.83
  6043.7 1784.17  6052.1 1789.34  6058.7 1799.87  6087.1 1808.86  6135.7 1830.77
#Mann= 9 ,-1 , 0
  4630.4      .1       0  4912.6    .035       0  4991.5    .035       0
  5003.3    .035       0    5152      .1       0  5295.9    .035       0
  5654.7     .07       0  5980.2    .035       0  6087.1      .1       0
#XS Ineff= 2 , 0
                         5562.24         1784.91
Permanent Ineff=
       F       F
Bank Sta=4991.5,5003.3
XS Rating Curve= 0 ,0
Exp/Cntr=0.3,0.1

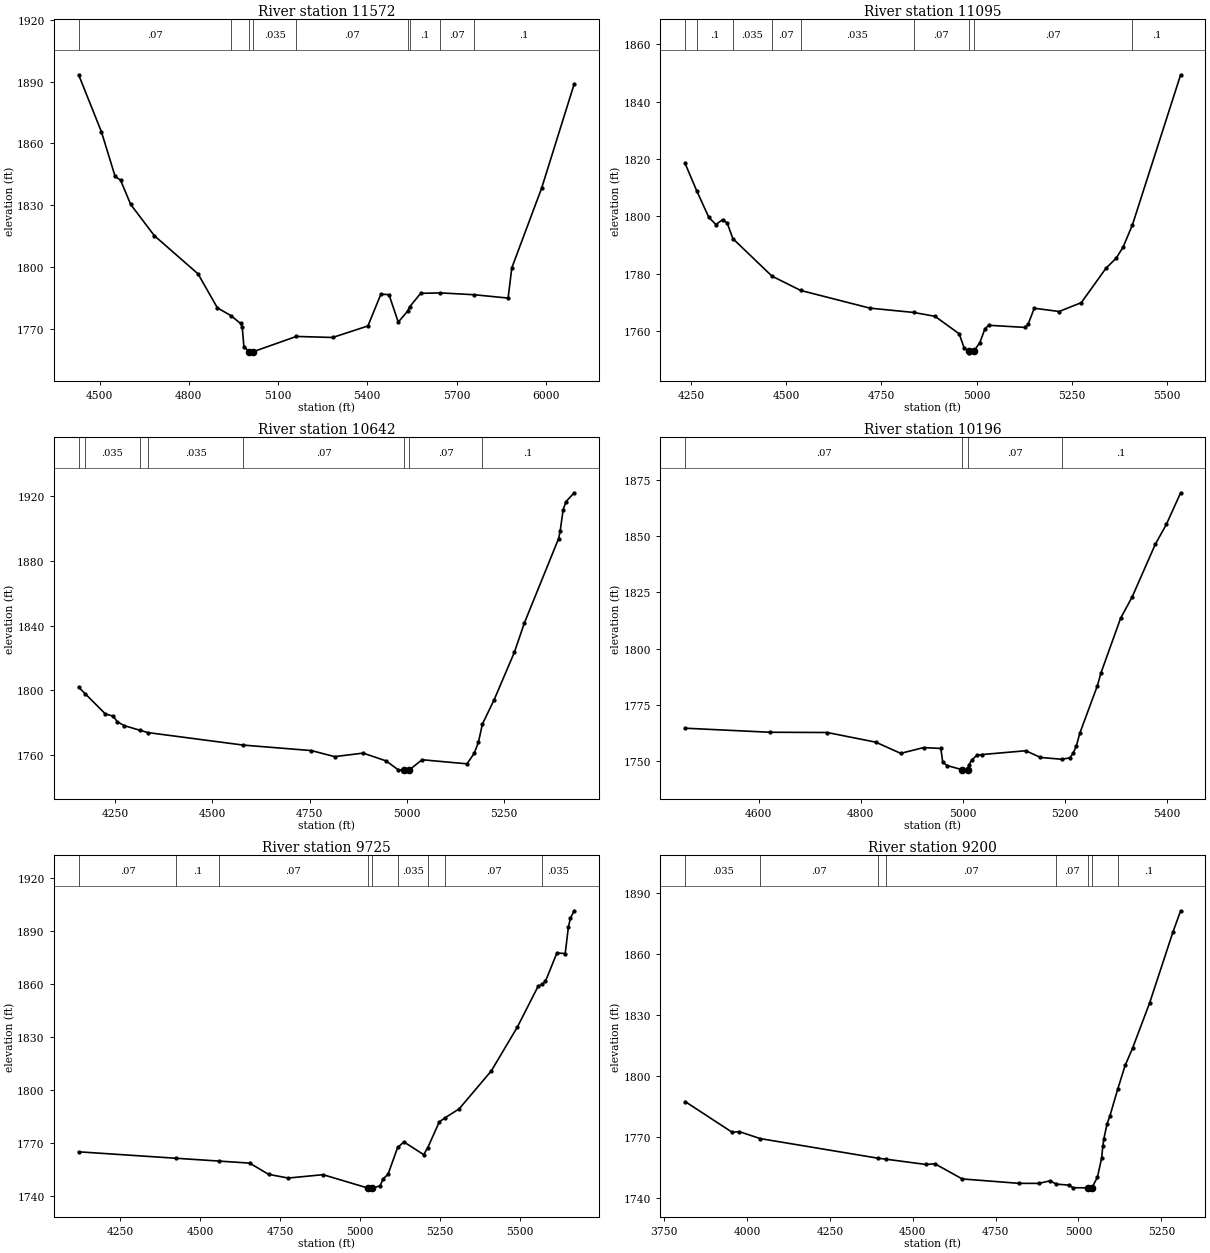
Type RM Length L Ch R = 1 ,11572   ,477,477,477
BEGIN DESCRIPTION:
Lamb Creek 23.0
END DESCRIPTION:
XS GIS Cut Line= 4
      1896575.02     13891574.98        1896975.       13891175.
        1897325.       13890875.      1897937.73     13890694.13
#Sta/Elev= 30
  4429.8 1893.38  4506.5 1865.62  4552.5 1843.95  4570.8 1842.12  4604.8 1830.34
  4684.1 1815.18  4831.1 1796.59  4896.2 1780.07    4942 1776.26  4973.9 1772.47
  4979.6 1770.83  4985.3 1761.13  5003.3  1758.7  5003.8  1758.2  5015.4  1758.7
  5161.6 1766.17  5283.6 1765.67  5402.1 1771.27  5445.6 1786.72  5472.9 1786.48
  5504.1 1773.11  5535.7 1778.51  5542.3 1780.57  5579.4 1787.13    5646 1787.34
  5758.9 1786.45  5873.2 1784.82  5885.7 1799.52  5985.8 1838.21  6095.3 1888.89
#Mann= 9 ,-1 , 0
  4429.8     .07       0    4942    .035       0  5003.3    .035       0
  5015.4    .035       0  5161.6     .07       0  5535.7    .035       0
  5542.3      .1       0    5646     .07       0  5758.9      .1       0
Bank Sta=5003.3,5015.4
XS Rating Curve= 0 ,0
Exp/Cntr=0.3,0.1

Type RM Length L Ch R = 1 ,11095   ,453,453,453
BEGIN DESCRIPTION:
Lamb Creek 22.0
END DESCRIPTION:
XS GIS Cut Line= 3
      1897013.51     13891925.35        1897425.       13891275.
        1897825.       13890925.
#Sta/Elev= 30
  4234.6 1818.43  4264.9 1808.94  4296.8 1799.62  4315.3 1797.11    4333 1798.77
  4345.1 1797.66    4360 1792.18  4462.7 1779.09  4538.1 1774.09    4720 1767.91
  4834.6 1766.41  4890.8 1765.06  4954.3 1758.95  4966.9 1754.12  4980.1 1752.81
  4980.6 1752.31  4992.3 1752.81  5008.5  1755.9  5022.1 1760.77  5031.8 1761.93
  5127.2 1761.19  5135.4 1762.35  5151.4 1767.89  5216.5 1766.74  5274.9 1769.83
  5339.8 1781.87  5366.6 1785.38  5384.4 1789.15  5409.1 1796.98  5535.7 1849.38
#Mann= 9 ,-1 , 0
  4234.6     .07       0  4264.9      .1       0    4360    .035       0
  4462.7     .07       0  4538.1    .035       0  4834.6     .07       0
  4980.1     .05       0  4992.3     .07       0  5409.1      .1       0
Bank Sta=4980.1,4992.3
XS Rating Curve= 0 ,0
Exp/Cntr=0.3,0.1

Type RM Length L Ch R = 1 ,10642   ,446,446,446
BEGIN DESCRIPTION:
Lamb Creek 21.0
END DESCRIPTION:
XS GIS Cut Line= 3
      1897252.18      13892044.4        1897825.       13891425.
      1898075.01     13891074.99
#Sta/Elev= 30
  4156.3 1802.04  4173.5 1797.91  4224.9 1785.56  4245.3 1784.14  4255.8 1780.65
  4273.5 1778.32    4313 1775.49  4334.6 1774.01  4579.2  1766.3  4754.8  1762.9
  4814.3 1759.17  4887.7 1761.34  4946.6 1756.54  4977.7 1751.06  4993.8  1750.9
  4994.3  1750.4  5006.1  1750.9  5039.1 1757.24  5154.6 1754.73  5173.3 1761.27
  5184.1 1768.19  5194.2 1779.26  5224.6 1794.39  5276.2 1823.48    5302 1841.62
  5390.1 1893.79  5394.2 1898.59  5401.6 1911.35    5409 1916.59  5430.1 1922.05
#Mann= 8 ,-1 , 0
  4156.3     .07       0  4173.5    .035       0    4313     .07       0
  4334.6    .035       0  4579.2     .07       0  4993.8     .05       0
  5006.1     .07       0  5194.2      .1       0
Bank Sta=4993.8,5006.1
XS Rating Curve= 0 ,0
Exp/Cntr=0.3,0.1

Type RM Length L Ch R = 1 ,10196   ,471,471,471
BEGIN DESCRIPTION:
Lamb Creek 20.0
END DESCRIPTION:
XS GIS Cut Line= 4
      1897779.46     13891991.57      1898061.49     13891776.34
        1898175.       13891625.      1898325.02     13891224.96
#Sta/Elev= 30
  4456.1 1764.46  4622.1 1762.65  4734.5 1762.54  4829.8 1758.23  4878.6 1753.24
  4923.6 1755.81  4957.3 1755.43  4961.1 1749.25  4969.6 1747.81    4999 1745.94
  4999.5 1745.44  5011.3 1745.94  5011.6 1747.83    5018 1750.24  5027.6 1752.33
  5037.2 1752.69  5123.7  1754.4  5152.6 1751.42  5194.2  1750.6  5210.2 1751.24
  5216.7 1753.33  5223.1 1756.64  5229.6 1762.16  5264.2 1783.45  5271.1 1789.08
  5309.6 1813.48  5332.6 1823.18  5377.8 1846.57  5399.3 1855.36  5427.3 1869.47
#Mann= 4 ,-1 , 0
  4456.1     .07       0    4999     .05       0  5011.3     .07       0
  5194.2      .1       0
Bank Sta=4999,5011.3
XS Rating Curve= 0 ,0
Exp/Cntr=0.3,0.1

Type RM Length L Ch R = 1 ,9725    ,525,525,525
BEGIN DESCRIPTION:
Lamb Creek 19.0
END DESCRIPTION:
XS GIS Cut Line= 3
      1897761.24     13892038.57        1898575.       13891725.
      1899199.57     13891463.22
#Sta/Elev= 30
  4120.7 1765.23  4426.4 1761.57    4560 1759.99  4655.2 1758.84    4715 1752.47
    4776  1750.4  4884.9  1752.3  5024.1  1744.8  5024.6  1744.3  5036.9  1744.8
    5063 1745.91  5072.7 1749.96    5088 1752.47    5118 1767.69  5137.8 1770.81
  5199.6 1763.62  5212.3  1767.6  5248.4 1782.18  5267.6 1784.59  5310.5 1789.52
    5411 1810.99  5492.4 1835.75  5557.4 1858.85  5570.4 1859.94  5580.1 1861.56
    5616 1877.63    5642 1877.31    5652 1892.43  5658.3 1897.31    5670 1901.48
#Mann= 9 ,-1 , 0
  4120.7     .07       0  4426.4      .1       0    4560     .07       0
  5024.1     .05       0  5036.9     .07       0    5118    .035       0
  5212.3      .1       0  5267.6     .07       0  5570.4    .035       0
Bank Sta=5024.1,5036.9
XS Rating Curve= 0 ,0
Exp/Cntr=0.3,0.1

Type RM Length L Ch R = 1 ,9200    ,593,593,593
BEGIN DESCRIPTION:
Lamb Creek 18.0
END DESCRIPTION:
XS GIS Cut Line= 3
      1897617.56     13892336.07       1898783.6      13892137.3
      1899075.04     13892024.98
#Sta/Elev= 30
  3813.1 1787.47  3955.3 1772.34  3976.6 1772.67  4040.2 1769.23  4394.9 1759.61
  4419.3 1759.12  4539.6 1756.52    4567 1756.85  4649.2 1749.41  4820.3 1747.24
  4880.5 1747.22  4913.9 1748.48  4933.2 1746.87  4971.1 1746.36  4983.9 1745.09
  5027.7 1745.04  5028.2 1744.54  5040.5 1745.04  5057.2 1750.24  5070.1  1759.8
  5073.3 1765.37  5076.5 1769.01  5086.1 1776.39  5094.4 1780.12  5118.5 1793.58
  5140.8 1805.21  5163.3 1813.72  5214.7 1835.94  5285.5 1871.02  5308.3 1881.26
#Mann= 8 ,-1 , 0
  3813.1    .035       0  4040.2     .07       0  4394.9      .1       0
  4419.3     .07       0  4933.2     .07       0  5027.7     .05       0
  5040.5     .07       0  5118.5      .1       0
Bank Sta=5027.7,5040.5
XS Rating Curve= 0 ,0
Exp/Cntr=0.3,0.1