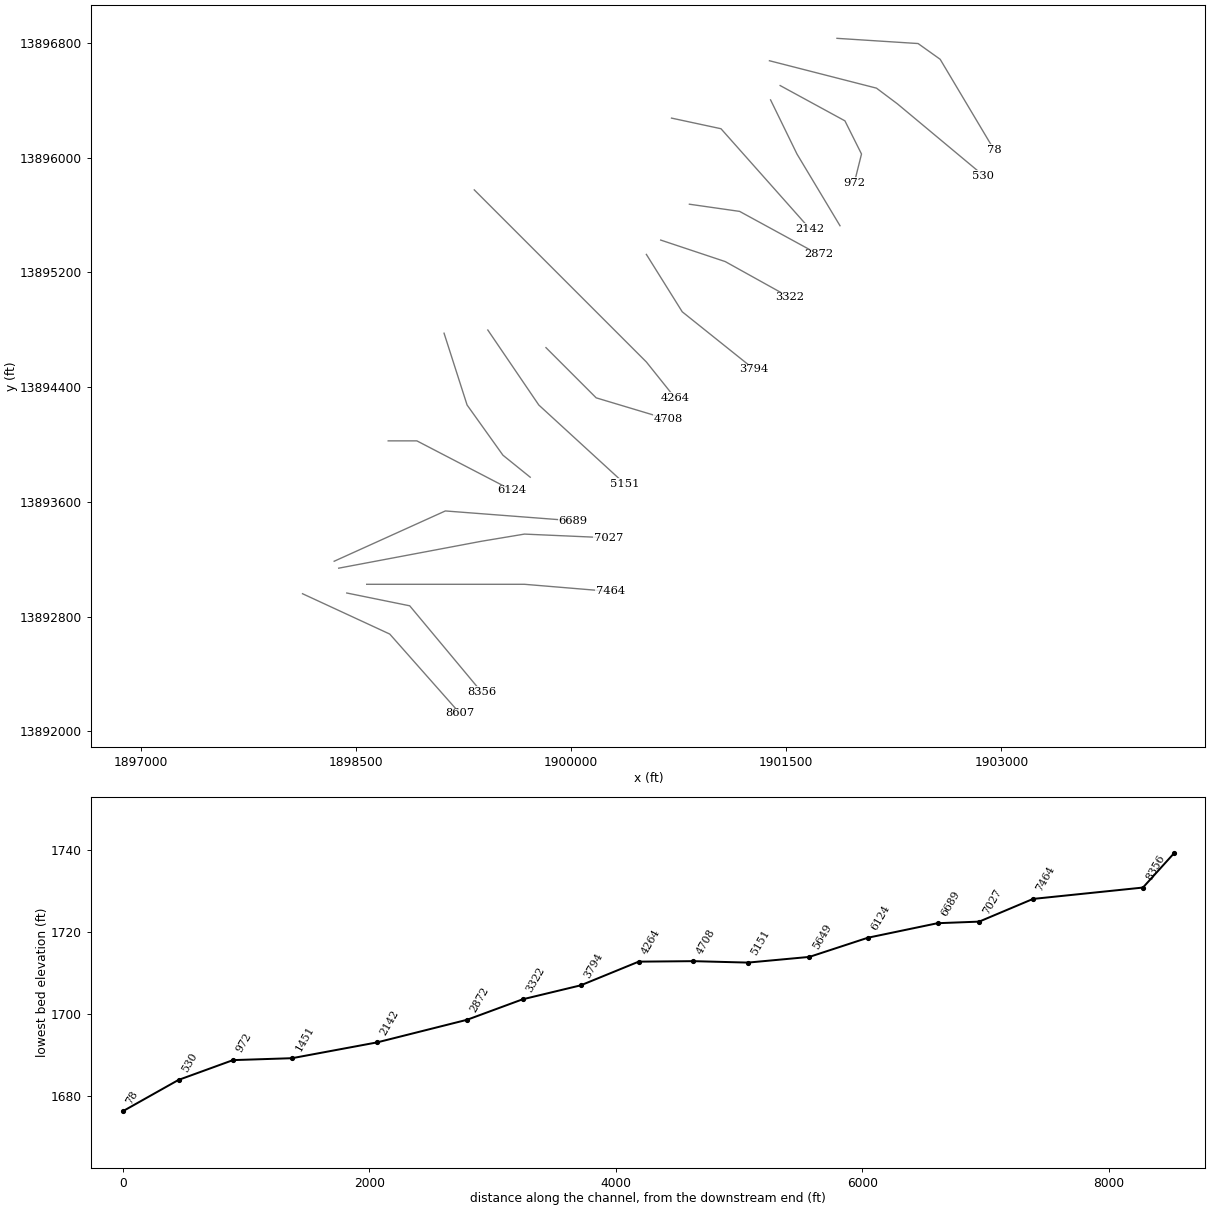
HEC-RAS study Lambs Creek.prj: Lambs Creek Base Level Engineering

--- Lambs Creek.g01 (geometry) --- (continued)

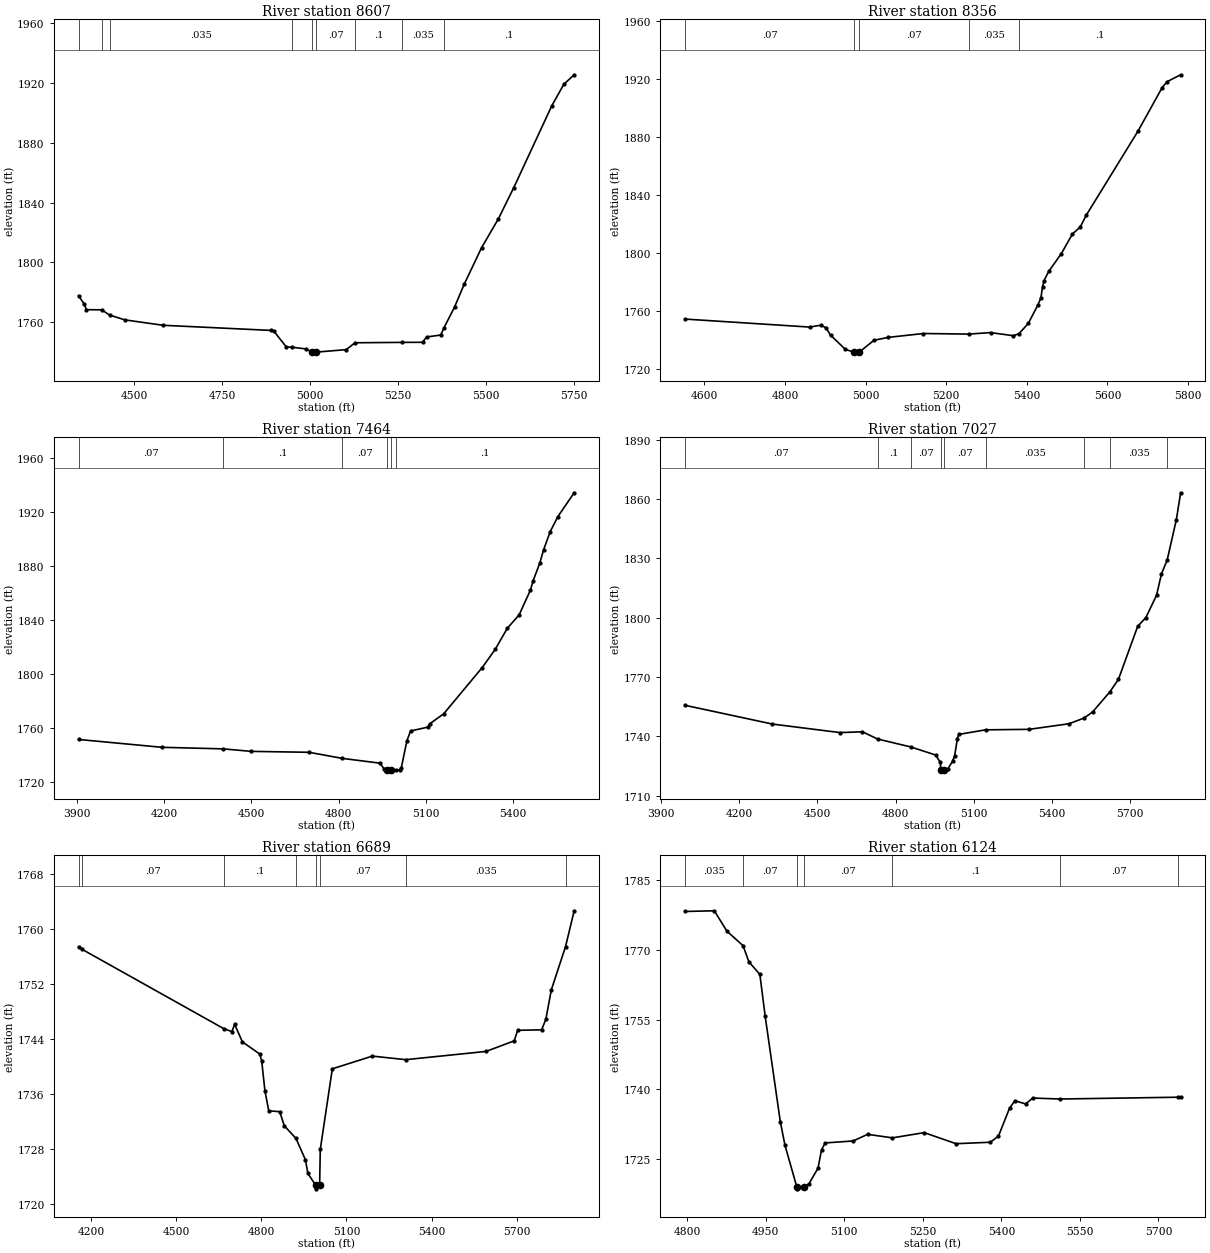
Type RM Length L Ch R = 1 ,8607    ,251,251,251
BEGIN DESCRIPTION:
Lamb Creek 17.0
END DESCRIPTION:
XS GIS Cut Line= 3
      1898127.62     13892959.29      1898735.83     13892677.98
        1899225.     13892125.01
#Sta/Elev= 30
  4342.7 1777.47  4358.3    1772  4364.9 1768.18    4408 1768.08    4431 1764.55
    4474 1761.34    4583 1757.72  4890.4 1754.27    4897 1753.92  4932.7 1743.28
    4949 1742.99  4989.6 1741.87  5005.1 1739.75  5005.6 1739.25  5018.6 1739.75
  5103.3  1741.4  5128.1    1746  5262.6 1746.26  5320.1 1746.31  5331.6 1749.88
  5371.7 1751.18  5381.4 1756.18  5411.1 1769.93  5438.3 1785.08  5487.8 1809.66
  5535.9 1829.15  5579.4 1849.95  5687.3 1904.74  5721.7 1919.24  5751.1 1925.61
#Mann= 9 ,-1 , 0
  4342.7    .035       0    4408     .07       0    4431    .035       0
    4949     .07       0  5005.1     .05       0  5018.6     .07       0
  5128.1      .1       0  5262.6    .035       0  5381.4      .1       0
Bank Sta=5005.1,5018.6
XS Rating Curve= 0 ,0
Exp/Cntr=0.3,0.1

Type RM Length L Ch R = 1 ,8356    ,892,892,892
BEGIN DESCRIPTION:
Lamb Creek 16.0
END DESCRIPTION:
XS GIS Cut Line= 3
      1898436.16     13892964.29        1898875.       13892875.
      1899375.03     13892274.97
#Sta/Elev= 30
  4552.5 1754.24  4861.3 1748.72  4888.8 1749.98  4901.6  1748.3  4913.3 1743.08
  4950.1 1733.28  4970.9  1731.4  4971.4  1730.9  4984.4  1731.4  5020.9 1739.59
  5056.1 1741.59  5143.7 1744.26  5255.8 1743.86  5309.9  1744.9  5366.4 1742.76
  5380.5 1744.12  5403.6 1751.25    5427 1763.77  5434.9 1768.88  5438.9 1776.48
  5442.7 1780.86  5454.4 1787.28  5485.7 1799.56    5513 1813.06  5532.5 1817.89
  5546.9 1825.86  5675.5 1884.11  5735.2 1914.12  5747.4 1918.33  5781.4 1923.15
#Mann= 5 ,-1 , 0
  4552.5     .07       0  4970.9     .05       0  4984.4     .07       0
  5255.8    .035       0  5380.5      .1       0
Bank Sta=4970.9,4984.4
XS Rating Curve= 0 ,0
Exp/Cntr=0.3,0.1

Type RM Length L Ch R = 1 ,7464    ,437,437,437
BEGIN DESCRIPTION:
Lamb Creek 15.0
END DESCRIPTION:
XS GIS Cut Line= 3
      1898575.03       13893025.        1899675.       13893025.
      1900275.05       13892975.
#Sta/Elev= 30
  3907.1 1751.36  4193.8 1745.55  4403.2  1744.4  4499.8 1742.55  4698.2 1741.86
  4812.6 1737.36  4941.5 1733.82  4956.5 1729.56  4967.7 1728.62  4968.2 1728.12
  4981.3 1728.62  4996.7 1728.72  5010.6 1728.85  5015.5 1730.39  5034.6 1750.39
  5047.3 1757.66  5106.9 1760.52  5112.9 1762.93  5161.1 1770.39  5293.5 1804.68
  5338.7 1818.37  5379.6  1833.8    5420 1843.61  5459.1  1862.1  5468.1  1868.9
  5490.7 1881.75  5504.3 1891.97  5526.8  1905.3  5553.1 1916.47  5609.2 1934.13
#Mann= 6 ,-1 , 0
  3907.1     .07       0  4403.2      .1       0  4812.6     .07       0
  4967.7     .05       0  4981.3     .07       0  4996.7      .1       0
Bank Sta=4967.7,4981.3
XS Rating Curve= 0 ,0
Exp/Cntr=0.3,0.1

Type RM Length L Ch R = 1 ,7027    ,338,338,338
BEGIN DESCRIPTION:
Lamb Creek 14.0
END DESCRIPTION:
XS GIS Cut Line= 4
      1898379.89     13893137.38        1899375.       13893325.
        1899675.       13893375.      1900258.85     13893349.24
#Sta/Elev= 30
  3992.1 1755.72  4326.8 1746.24  4586.2 1741.92  4672.5 1742.31  4730.9 1738.66
  4858.5 1734.64  4953.3 1730.57  4971.6  1726.8  4972.9 1723.07  4973.4 1722.57
  4986.5 1723.07  5000.3 1723.54  5018.5 1727.52  5026.3 1730.23  5036.7 1738.86
  5041.7 1740.99  5144.9 1743.31  5312.4 1743.57  5465.5  1746.4  5523.4 1749.33
  5555.6 1752.36  5622.2 1762.58  5654.7 1768.87  5728.6 1795.71    5760  1800.1
  5800.8 1811.38  5819.8 1822.22  5841.6 1829.18  5876.9 1849.65  5893.3 1863.23
#Mann= 9 ,-1 , 0
  3992.1     .07       0  4730.9      .1       0  4858.5     .07       0
  4972.9     .05       0  4986.5     .07       0  5144.9    .035       0
  5523.4     .07       0  5622.2    .035       0  5841.6      .1       0
Bank Sta=4972.9,4986.5
XS Rating Curve= 0 ,0
Exp/Cntr=0.3,0.1

Type RM Length L Ch R = 1 ,6689    ,565,565,565
BEGIN DESCRIPTION:
Lamb Creek 13.0
END DESCRIPTION:
XS GIS Cut Line= 3
      1898348.39     13893185.75      1899123.38     13893536.36
      1900014.85     13893467.97
#Sta/Elev= 30
  4156.9 1757.39  4168.3 1757.04  4667.1  1745.5  4696.6 1745.05  4706.1 1746.12
  4733.5 1743.56  4794.6 1741.79  4801.4 1740.82  4812.7 1736.47  4826.3 1733.53
  4865.2  1733.4  4880.7 1731.37  4922.2 1729.51  4955.5  1726.4    4964 1724.43
  4991.8 1722.68  4992.3 1722.18  5005.4 1722.68  5007.7 1727.92  5050.1 1739.64
  5191.1 1741.49  5308.4 1740.97  5591.3 1742.17  5690.6 1743.71  5702.6 1745.24
  5786.9 1745.31  5801.9 1746.84  5821.2 1751.13  5871.2 1757.42  5901.6 1762.63
#Mann= 8 ,-1 , 0
  4156.9    .035       0  4168.3     .07       0  4667.1      .1       0
  4922.2     .07       0  4991.8     .05       0  5005.4     .07       0
  5308.4    .035       0  5871.2     .07       0
Bank Sta=4991.8,5005.4
XS Rating Curve= 0 ,0
Exp/Cntr=0.3,0.1

Type RM Length L Ch R = 1 ,6124    ,475,475,475
BEGIN DESCRIPTION:
Lamb Creek 12.0
END DESCRIPTION:
XS GIS Cut Line= 3
      1898724.99       13894025.        1898925.       13894025.
      1899587.31     13893680.83
#Sta/Elev= 30
  4795.9 1778.29  4851.7 1778.44  4875.7 1774.06  4906.6 1770.94  4917.7 1767.46
  4938.7 1764.75  4948.8 1755.79  4977.7 1733.09  4986.7 1727.98    5009 1719.13
  5009.5 1718.63  5022.9 1719.13  5032.4  1719.7  5049.7 1723.07  5056.5 1727.01
  5063.2  1728.5  5116.9 1728.93  5144.4 1730.35    5192  1729.6  5252.6 1730.72
  5313.4 1728.34  5378.5 1728.65  5394.2 1729.93  5415.7 1736.02  5425.8 1737.58
  5446.1  1736.9    5460 1738.16    5512 1737.95  5737.9 1738.34  5742.3 1738.42
#Mann= 7 ,-1 , 0
  4795.9    .035       0  4906.6     .07       0    5009     .05       0
  5022.9     .07       0    5192      .1       0    5512     .07       0
  5737.9    .035       0
Bank Sta=5009,5022.9
XS Rating Curve= 0 ,0
Exp/Cntr=0.3,0.1

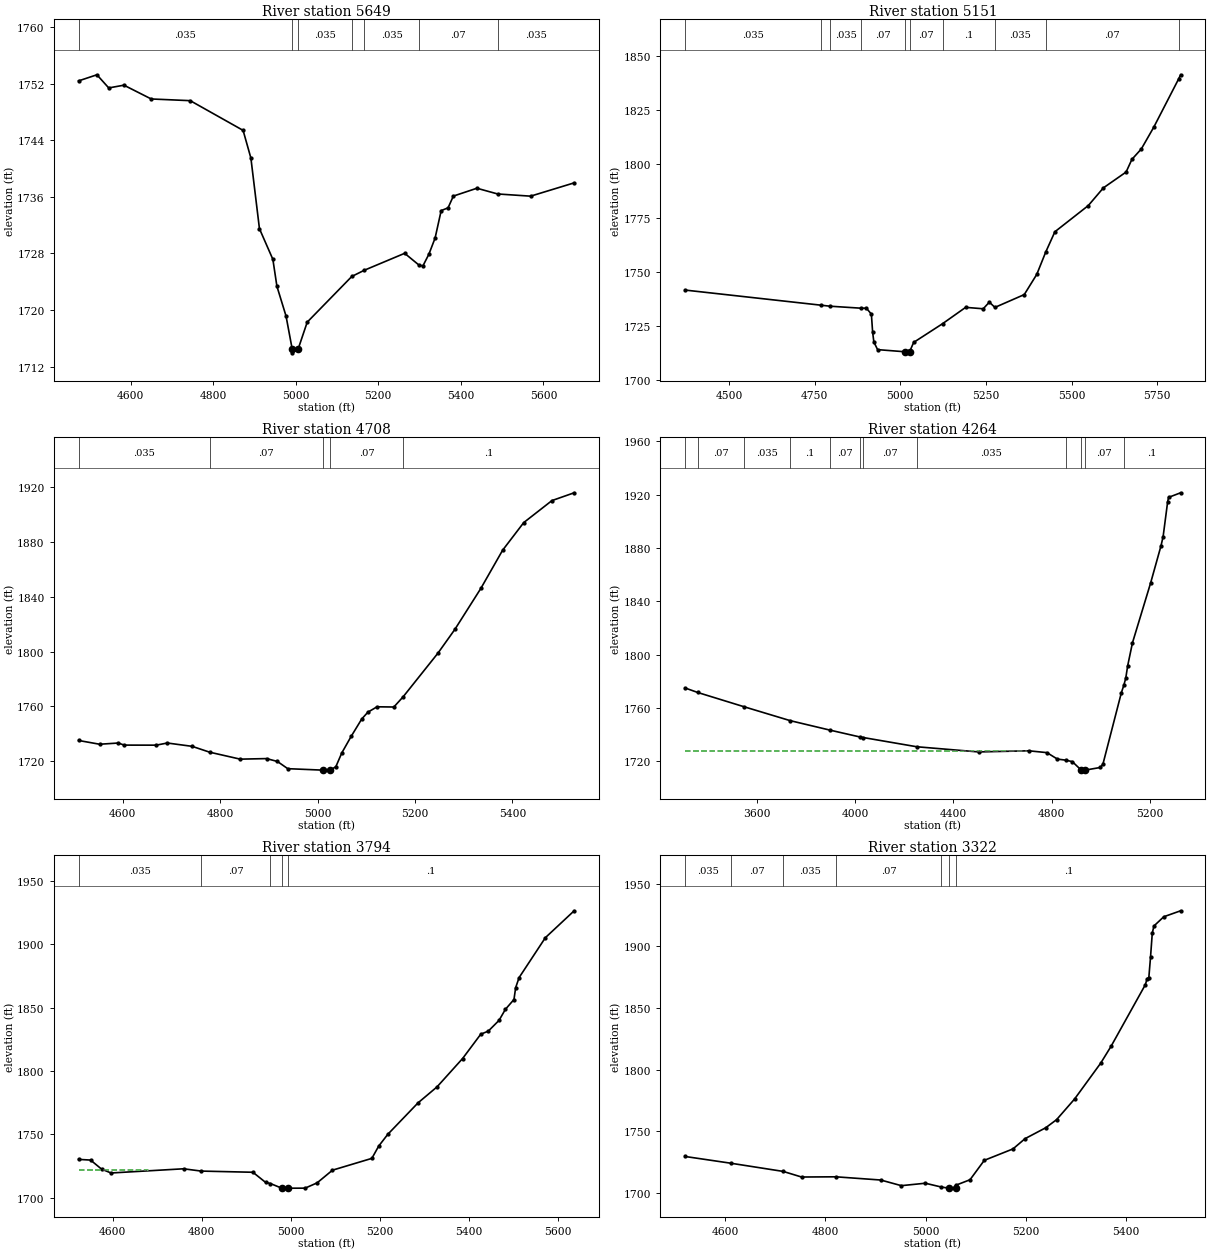
Type RM Length L Ch R = 1 ,5649    ,498,498,498
BEGIN DESCRIPTION:
Lamb Creek 11.0
END DESCRIPTION:
XS GIS Cut Line= 4
      1899114.47     13894775.63        1899275.       13894275.
        1899525.       13893925.      1899715.11     13893771.65
#Sta/Elev= 30
  4474.3 1752.39  4518.6 1753.25  4547.2 1751.39    4584 1751.78  4650.1 1749.83
  4744.6 1749.59  4872.6 1745.39  4891.5 1741.47  4912.2 1731.49  4944.7 1727.16
  4954.5 1723.35  4976.6 1719.14  4991.6 1714.44  4992.1 1713.94  5005.7 1714.44
  5027.9 1718.28  5135.9 1724.74  5166.3 1725.62  5263.9 1728.01  5298.7 1726.34
  5308.1 1726.23  5322.6 1727.89  5337.6 1730.17  5352.3 1734.05    5369 1734.44
  5381.8  1736.1  5438.8 1737.21  5489.1  1736.4  5568.9 1736.09  5674.4 1737.97
#Mann= 7 ,-1 , 0
  4474.3    .035       0  4991.6    .035       0  5005.7    .035       0
  5135.9     .07       0  5166.3    .035       0  5298.7     .07       0
  5489.1    .035       0
Bank Sta=4991.6,5005.7
XS Rating Curve= 0 ,0
Exp/Cntr=0.3,0.1

Type RM Length L Ch R = 1 ,5151    ,443,443,443
BEGIN DESCRIPTION:
Lamb Creek 10.0
END DESCRIPTION:
XS GIS Cut Line= 3
       1899419.5     13894797.92        1899775.       13894275.
      1900375.03     13893724.97
#Sta/Elev= 30
  4372.1 1741.64  4770.1 1734.61  4795.3 1734.16  4886.6 1733.23  4901.2 1733.25
  4915.8 1730.48  4919.4 1722.21    4923 1717.59  4933.9 1714.04  5013.2 1713.05
  5013.7 1712.55  5027.3 1713.05  5039.2 1717.39  5123.4 1726.04  5190.9 1733.63
  5242.2 1732.97  5260.1 1736.06  5276.3  1733.6    5362 1739.55  5398.5 1748.91
  5424.7 1759.28  5451.4 1768.67  5548.8 1780.79  5592.9    1789  5659.2 1796.34
  5676.2 1802.22  5703.7 1807.06  5739.9  1817.1  5812.2 1839.38  5818.4 1841.42
#Mann= 10 ,-1 , 0
  4372.1    .035       0  4770.1     .07       0  4795.3    .035       0
  4886.6     .07       0  5013.2     .05       0  5027.3     .07       0
  5123.4      .1       0  5276.3    .035       0  5424.7     .07       0
  5812.2      .1       0
Bank Sta=5013.2,5027.3
XS Rating Curve= 0 ,0
Exp/Cntr=0.3,0.1

Type RM Length L Ch R = 1 ,4708    ,444,444,444
BEGIN DESCRIPTION:
Lamb Creek 9.0
END DESCRIPTION:
XS GIS Cut Line= 3
      1899824.98     13894675.02        1900175.       13894325.
      1900674.98     13894175.01
#Sta/Elev= 30
  4509.6 1735.08  4552.7 1732.33  4590.9 1733.22  4603.1  1731.7  4668.8 1731.66
  4691.6 1733.23  4742.5  1730.8  4778.4 1726.54  4841.2 1721.44  4895.3 1721.85
  4917.6 1719.74  4938.8 1714.48  5011.6  1713.4  5012.1  1712.9  5025.8  1713.4
  5037.5 1715.93  5049.7 1725.99  5068.8 1738.01  5090.7 1750.81  5103.2 1755.75
    5122 1759.69  5156.5 1759.53  5175.5 1766.96  5247.1 1798.92  5281.8 1816.27
    5335 1846.14  5379.8 1874.11  5423.1 1894.28    5481 1910.35  5526.6 1916.05
#Mann= 5 ,-1 , 0
  4509.6    .035       0  4778.4     .07       0  5011.6     .05       0
  5025.8     .07       0  5175.5      .1       0
Bank Sta=5011.6,5025.8
XS Rating Curve= 0 ,0
Exp/Cntr=0.3,0.1

Type RM Length L Ch R = 1 ,4264    ,470,470,470
BEGIN DESCRIPTION:
Lamb Creek 8.0
END DESCRIPTION:
XS GIS Cut Line= 3
      1899325.03     13895774.97        1900525.       13894575.
      1900725.01     13894324.98
#Sta/Elev= 30
  3307.6 1774.96  3359.1 1771.57  3546.7 1760.92  3735.6 1750.43  3898.3 1743.29
  4019.1  1738.2  4033.1 1737.76  4250.8 1730.85  4502.1 1726.97  4706.9 1727.82
  4780.6 1726.44    4823 1721.61  4857.7 1720.78    4884 1719.67  4920.4 1713.28
  4920.9 1712.78  4934.6 1713.28  4998.5 1715.32  5008.6  1717.9  5083.6 1771.47
  5093.7 1777.07  5101.5 1782.46  5109.4  1791.8  5128.6 1808.79  5202.7  1853.8
    5245 1881.73  5253.5 1888.58  5271.9 1914.66  5275.7 1917.99  5324.8 1921.43
#Mann= 12 ,-1 , 0
  3307.6    .035       0  3359.1     .07       0  3546.7    .035       0
  3735.6      .1       0  3898.3     .07       0  4019.1      .1       0
  4033.1     .07       0  4250.8    .035       0  4857.7     .07       0
  4920.4     .05       0  4934.6     .07       0  5093.7      .1       0
#XS Ineff= 2 , 0
          4698.3 1727.94
Permanent Ineff=
       F       F
Bank Sta=4920.4,4934.6
XS Rating Curve= 0 ,0
Exp/Cntr=0.3,0.1

Type RM Length L Ch R = 1 ,3794    ,472,472,472
BEGIN DESCRIPTION:
Lamb Creek 7.0
END DESCRIPTION:
XS GIS Cut Line= 3
      1900524.99     13895325.01        1900775.       13894925.
      1901274.98     13894525.02
#Sta/Elev= 30
  4523.7 1730.22  4550.5 1729.69  4575.2 1722.54  4596.4  1719.5  4759.2 1722.81
  4798.7    1721  4914.8 1720.07  4943.1 1712.12  4954.1 1711.17  4979.7 1707.49
  4980.2 1706.99    4994 1707.49  5031.9 1707.53  5058.9 1711.71  5093.3 1721.71
  5181.7 1731.03  5197.1 1740.74  5217.4 1749.98  5285.4 1774.85  5327.9 1787.42
  5385.3 1809.81    5426 1828.96    5443 1831.45  5467.1 1839.92  5481.4 1848.64
  5500.6 1856.38  5504.4 1865.74  5512.1 1873.68  5571.1 1905.18  5635.7 1926.39
#Mann= 5 ,-1 , 0
  4523.7    .035       0  4798.7     .07       0  4954.1      .1       0
  4979.7     .05       0    4994      .1       0
#XS Ineff= 2 , 0
         4678.32 1721.96
Permanent Ineff=
       F       F
Bank Sta=4979.7,4994
XS Rating Curve= 0 ,0
Exp/Cntr=0.3,0.1

Type RM Length L Ch R = 1 ,3322    ,450,450,450
BEGIN DESCRIPTION:
Lamb Creek 6.0
END DESCRIPTION:
XS GIS Cut Line= 3
      1900624.99       13895425.        1901075.       13895275.
      1901524.97     13895025.01
#Sta/Elev= 30
  4519.8 1729.77  4610.7 1724.33  4715.7 1717.67  4752.2 1713.14  4820.8 1713.31
  4910.3 1710.71  4951.4 1706.14  4999.3 1708.11  5031.5    1705    5047 1704.07
  5047.5 1703.57  5061.3 1704.07  5061.4 1706.69  5088.5 1710.93    5117 1726.65
  5174.3  1735.9  5198.3 1744.18  5239.5    1753  5261.3 1759.58  5297.2 1776.29
  5349.3 1805.31  5369.9 1818.88  5438.5 1868.88    5442 1873.75  5445.4 1874.49
  5448.8 1891.22  5452.3 1910.69  5455.7 1916.43  5475.3 1923.86  5508.9 1928.69
#Mann= 7 ,-1 , 0
  4519.8    .035       0  4610.7     .07       0  4715.7    .035       0
  4820.8     .07       0  5031.5      .1       0    5047     .05       0
  5061.3      .1       0
Bank Sta=5047,5061.3
XS Rating Curve= 0 ,0
Exp/Cntr=0.3,0.1

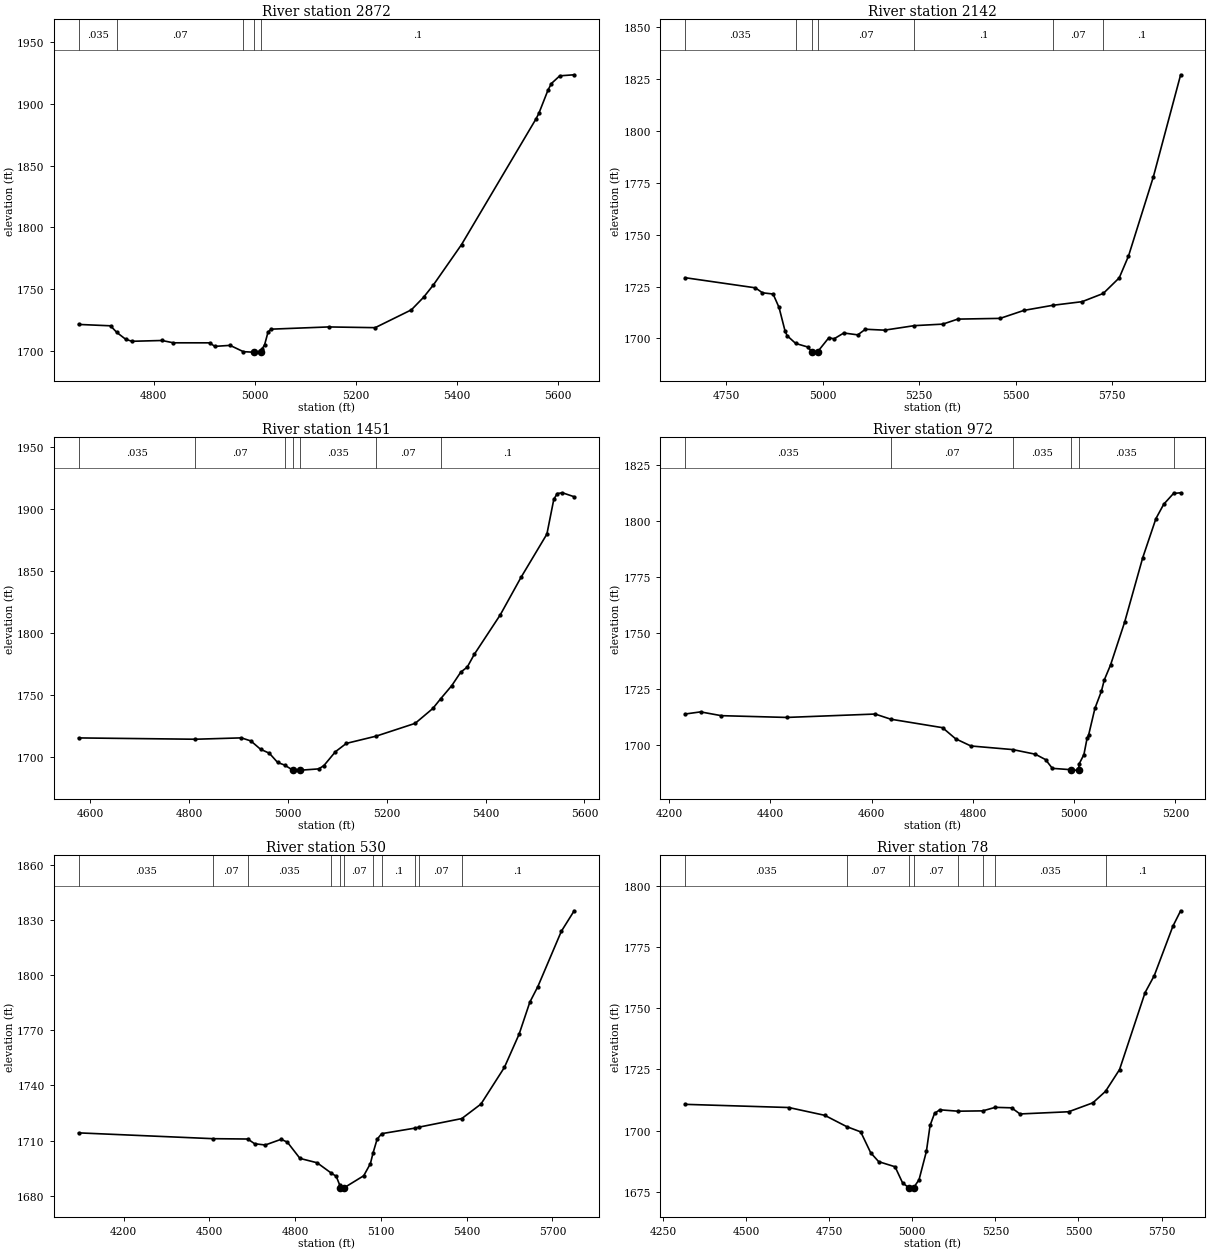
Type RM Length L Ch R = 1 ,2872    ,730,730,730
BEGIN DESCRIPTION:
Lamb Creek 5.0
END DESCRIPTION:
XS GIS Cut Line= 3
      1900824.98       13895675.        1901175.       13895625.
      1901725.02     13895324.99
#Sta/Elev= 30
  4651.9 1721.55    4715 1720.44  4727.5 1715.03  4745.3 1709.45  4757.5 1707.91
  4816.7 1708.56  4839.3 1706.68  4911.3 1706.66  4921.1 1703.79  4951.4 1704.62
  4977.7 1699.52  4998.9 1699.07  4999.4 1698.57  5013.2 1699.07  5015.2 1702.02
  5019.7 1705.05  5026.5 1715.34  5032.5 1717.72  5146.1 1719.52  5238.4 1718.93
    5310 1733.35  5334.1 1743.49  5353.6 1753.52  5409.2 1786.12  5556.2 1887.59
  5562.1 1892.23  5580.1 1910.97  5586.9  1916.4  5603.5 1922.64    5632 1923.49
#Mann= 5 ,-1 , 0
  4651.9    .035       0  4727.5     .07       0  4977.7      .1       0
  4998.9     .05       0  5013.2      .1       0
Bank Sta=4998.9,5013.2
XS Rating Curve= 0 ,0
Exp/Cntr=0.3,0.1

Type RM Length L Ch R = 1 ,2142    ,691,691,691
BEGIN DESCRIPTION:
Lamb Creek 4.0
END DESCRIPTION:
XS GIS Cut Line= 3
      1900700.36     13896275.38      1901045.27     13896201.25
      1901664.22     13895504.31
#Sta/Elev= 30
  4643.1 1729.28  4825.3  1724.4  4843.7    1722  4871.3 1721.41  4886.7 1714.92
    4902 1703.77  4907.6 1701.32  4929.8 1697.58  4960.6 1695.88    4972 1693.54
  4972.5 1693.04  4986.6 1693.54  5015.8 1700.33  5029.3  1699.8  5054.6 1702.61
  5090.8 1701.71  5110.6 1704.42  5160.3 1703.98  5237.7 1706.16  5311.4 1706.89
  5350.1 1709.31  5459.9 1709.66  5521.8 1713.52  5596.8 1715.98  5672.5 1717.72
  5727.4 1721.69  5768.8 1729.21  5792.8 1739.72  5857.1 1777.83    5928 1827.16
#Mann= 7 ,-1 , 0
  4643.1    .035       0  4929.8     .07       0    4972     .05       0
  4986.6     .07       0  5237.7      .1       0  5596.8     .07       0
  5727.4      .1       0
Bank Sta=4972,4986.6
XS Rating Curve= 0 ,0
Exp/Cntr=0.3,0.1

Type RM Length L Ch R = 1 ,1451    ,479,479,479
BEGIN DESCRIPTION:
Lamb Creek 3.0
END DESCRIPTION:
XS GIS Cut Line= 3
      1901391.03     13896402.31        1901575.       13896025.
      1901875.02     13895524.97
#Sta/Elev= 30
  4576.2 1715.69  4812.7 1714.63  4905.5 1715.73  4924.8 1713.26  4944.3 1706.57
  4962.2 1703.35  4978.9 1695.94    4993 1693.82  5009.9 1689.67  5010.4 1689.17
  5024.5 1689.67  5062.1 1690.74  5072.6 1693.41  5095.9 1704.57    5118 1711.28
  5178.4 1717.13  5257.3 1727.43    5293  1739.4  5308.8 1747.19  5331.5 1757.89
  5349.6 1768.69  5362.7 1772.74  5376.9 1782.99  5429.4 1814.75  5471.4 1844.96
  5523.9  1879.9  5537.9 1907.96  5544.9 1912.58  5555.4 1913.18  5579.1 1909.98
#Mann= 7 ,-1 , 0
  4576.2    .035       0  4812.7     .07       0    4993    .035       0
  5009.9    .035       0  5024.5    .035       0  5178.4     .07       0
  5308.8      .1       0
Bank Sta=5009.9,5024.5
XS Rating Curve= 0 ,0
Exp/Cntr=0.3,0.1

Type RM Length L Ch R = 1 ,972     ,442,442,442
BEGIN DESCRIPTION:
Lamb Creek 2.0
END DESCRIPTION:
XS GIS Cut Line= 4
      1901457.73     13896502.35      1901909.34     13896256.31
        1902025.       13896025.      1901974.99     13895824.96
#Sta/Elev= 30
  4231.4 1713.99  4261.9 1714.94  4302.8 1713.26  4432.1 1712.47  4606.9 1713.98
  4637.9 1711.68  4740.1 1707.91  4765.8 1702.98    4796 1699.77  4878.7 1698.16
  4923.4  1696.1  4943.6  1693.7    4957 1689.81  4994.1  1689.2  4994.6  1688.7
  5008.8  1689.2  5010.2 1691.89  5019.4 1695.95  5025.6 1703.15  5028.7 1704.65
  5041.1 1716.48    5054 1724.18  5059.6 1729.14    5072 1735.81  5099.8 1754.85
  5135.6 1783.57  5161.7    1801  5177.1 1807.37  5196.4 1812.17  5210.5 1812.47
#Mann= 6 ,-1 , 0
  4231.4    .035       0  4637.9     .07       0  4878.7    .035       0
  4994.1    .035       0  5008.8    .035       0  5196.4      .1       0
Bank Sta=4994.1,5008.8
XS Rating Curve= 0 ,0
Exp/Cntr=0.3,0.1

Type RM Length L Ch R = 1 ,530     ,452,452,452
BEGIN DESCRIPTION:
Lamb Creek 1.0
END DESCRIPTION:
XS GIS Cut Line= 4
      1901383.13     13896675.38      1902129.28     13896484.29
        1902275.       13896375.      1902874.99       13895875.
#Sta/Elev= 30
  4042.8 1714.26  4513.5  1711.1  4634.5 1710.92  4658.4 1708.35  4695.5 1707.67
  4751.3 1710.77    4773  1709.2    4817 1700.39    4877 1698.02  4926.1 1692.46
  4943.9 1690.65  4955.8 1686.02  4955.9 1684.36  4956.4 1683.86  4970.7 1684.36
    5040 1690.97  5063.4 1697.55  5072.7 1703.36  5086.8 1710.78  5102.8 1713.83
  5220.7 1716.88  5234.6 1717.41  5383.1 1722.03  5450.1  1729.9    5532 1749.79
  5583.6 1767.88  5621.1 1785.26  5649.2 1793.74  5731.3 1823.74  5776.2 1834.89
#Mann= 11 ,-1 , 0
  4042.8    .035       0  4513.5     .07       0  4634.5    .035       0
  4926.1     .07       0  4955.9     .05       0  4970.7     .07       0
  5072.7    .035       0  5102.8      .1       0  5220.7    .035       0
  5234.6     .07       0  5383.1      .1       0
Bank Sta=4955.9,4970.7
XS Rating Curve= 0 ,0
Exp/Cntr=0.3,0.1

Type RM Length L Ch R = 1 ,78      ,0,0,0
BEGIN DESCRIPTION:
Lamb Creek 0.0
END DESCRIPTION:
XS GIS Cut Line= 4
      1901853.95     13896831.54      1902419.42     13896795.24
       1902573.4     13896685.48      1902950.08     13896053.33
#Sta/Elev= 30
    4316 1710.73  4628.2 1709.43  4736.4 1706.24  4802.2 1701.64  4844.6 1699.47
  4874.7 1690.94  4898.7 1687.31    4948 1685.22  4970.8 1678.59  4989.2  1676.7
  4989.7  1676.2    5004  1676.7  5020.2 1679.93  5042.3  1691.5  5053.4 1702.12
  5066.8 1707.02  5082.4  1708.5  5137.3 1707.93  5211.7 1708.06  5249.6  1709.5
  5298.9 1709.31  5323.9  1706.8  5470.4  1707.7  5543.4 1711.35  5581.5 1716.05
  5623.7 1724.94  5700.5 1756.38  5728.3 1763.36  5784.3 1783.53  5807.6 1789.83
#Mann= 8 ,-1 , 0
    4316    .035       0  4802.2     .07       0  4989.2     .05       0
    5004     .07       0  5137.3      .1       0  5211.7     .07       0
  5249.6    .035       0  5581.5      .1       0
Bank Sta=4989.2,5004
XS Rating Curve= 0 ,0
Exp/Cntr=0.3,0.1

Chan Stop Cuts=-1
Use User Specified Reach Order=0
Composite Channel Slope=5