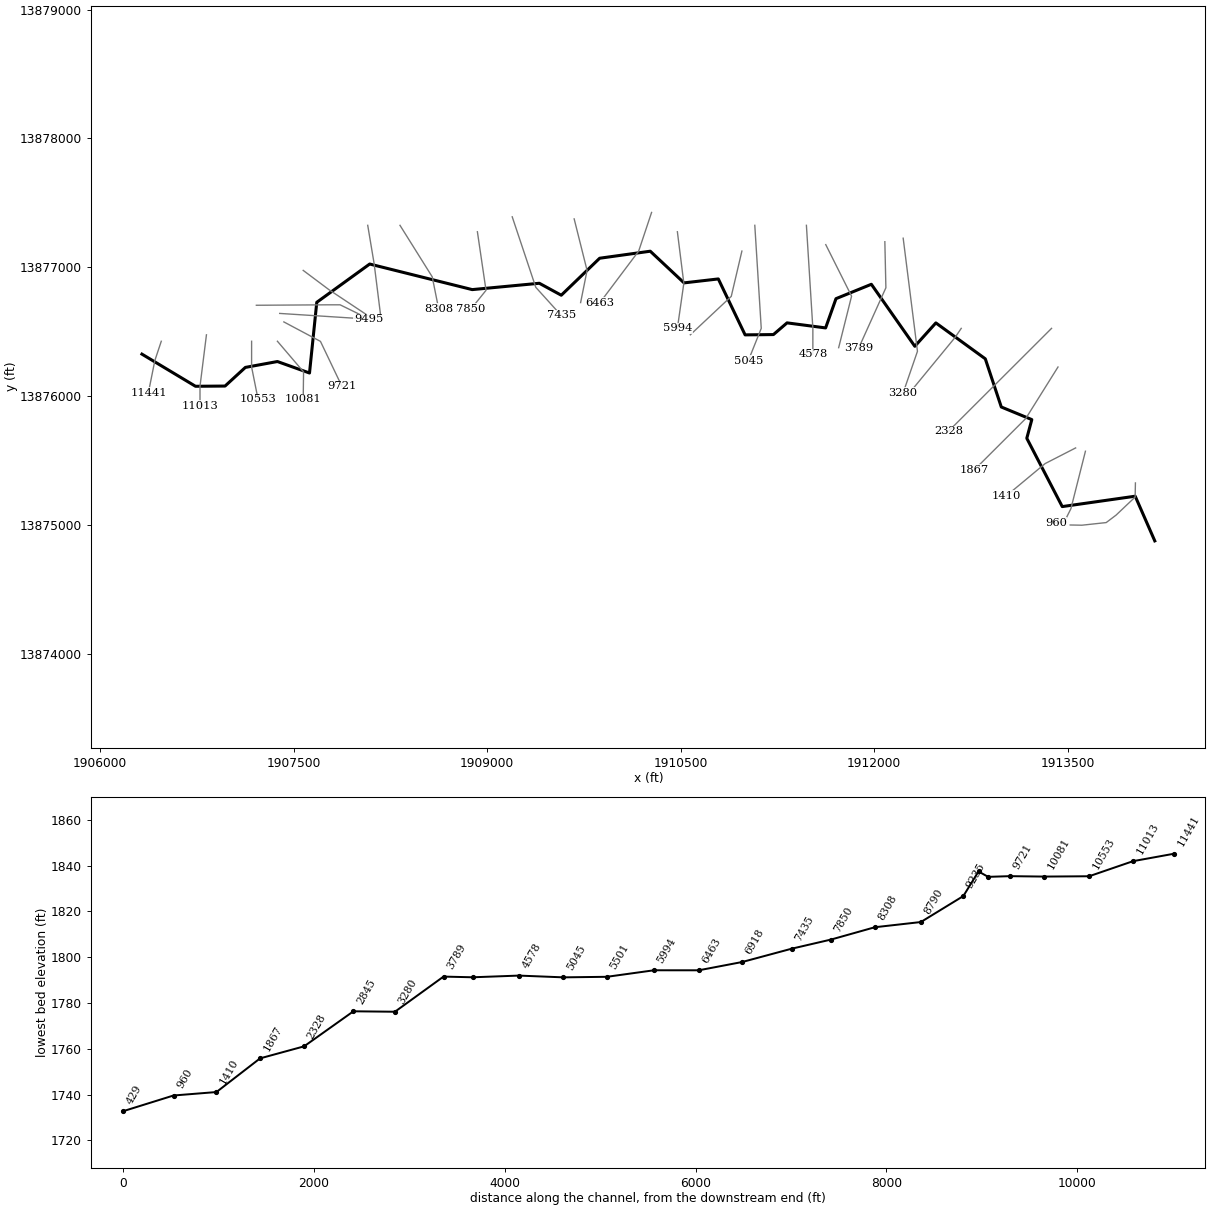
--- Lin Prong.prj (project) ---

Proj Title=Lin Prong Base Level Engineering
Current Plan=p01
Default Exp/Contr=0.3,0.1
English Units
Geom File=g01
Flow File=f01
Plan File=p01
BEGIN DESCRIPTION:
Lin Prong
END DESCRIPTION:

--- Lin Prong.p01 (plan) ---

Plan Title=Multiple Run
Short Identifier=Multiple
Geom File=g01
Flow File=f01
Subcritical Flow
K Sum by GR= 0
Std Step Tol= 0.01
Critical Tol= 0.01
Num of Std Step Trials= 20
Max Error Tol= 0.3
Flow Tol Ratio= 0.001
Split Flow NTrial= 30
Split Flow Tol= 0.02
Split Flow Ratio= 0.02
Log Output Level= 0
Friction Slope Method= 1
Unsteady Friction Slope Method= 2
Unsteady Bridges Friction Slope Method= 1
Parabolic Critical Depth
Global Vel Dist=  1 , 1 , 1
Global Log Level= 0
CheckData=True
Encroach Param= -1, 0, 0, 0
BEGIN DESCRIPTION:
Multiple Run
END DESCRIPTION:

--- Lin Prong.f01 (steady flow) ---

Flow Title=Multiple
Number of Profiles=7
Profile Names=10-year,25-year,50-year,1pct_min,100-year,1pct_plu,500-year
River Rch & RM= Lin Prong,Reach-1,11441
    2252    3940    5586    3820    7621   15206   14014
Boundary for River Rch & Prof#=Lin Prong,Reach-1,1
Up Type=0
Dn Type=3
Dn Slope=0.005
Boundary for River Rch & Prof#=Lin Prong,Reach-1,2
Up Type=0
Dn Type=3
Dn Slope=0.005
Boundary for River Rch & Prof#=Lin Prong,Reach-1,3
Up Type=0
Dn Type=3
Dn Slope=0.005
Boundary for River Rch & Prof#=Lin Prong,Reach-1,4
Up Type=0
Dn Type=3
Dn Slope=0.005
Boundary for River Rch & Prof#=Lin Prong,Reach-1,5
Up Type=0
Dn Type=3
Dn Slope=0.005
Boundary for River Rch & Prof#=Lin Prong,Reach-1,6
Up Type=0
Dn Type=3
Dn Slope=0.005
Boundary for River Rch & Prof#=Lin Prong,Reach-1,7
Up Type=0
Dn Type=3
Dn Slope=0.005

--- Lin Prong.g01 (geometry) ---

Geom Title=Existing Conditions

River Reach=Lin Prong,Reach-1
Reach XY= 30
      1906325.00     13876325.00      1906740.16     13876075.38
      1906969.15     13876077.06      1907126.65     13876221.84
      1907375.00     13876267.50      1907623.75     13876178.36
      1907680.11     13876727.30      1908090.22     13877024.48
      1908884.85     13876825.93      1909404.91     13876875.11
      1909575.09     13876782.29      1909872.57     13877069.48
      1910264.72     13877124.01      1910526.64     13876878.14
      1910792.23     13876908.76      1910999.87     13876474.47
      1911219.36     13876476.79      1911324.90     13876567.67
      1911623.78     13876528.43      1911704.35     13876755.58
      1911978.42     13876867.24      1912315.13     13876385.90
      1912478.32     13876567.42      1912861.51     13876288.56
      1912985.48     13875914.49      1913222.02     13875816.66
      1913183.04     13875671.69      1913457.86     13875141.27
      1914023.38     13875221.88      1914175.00     13874875.00

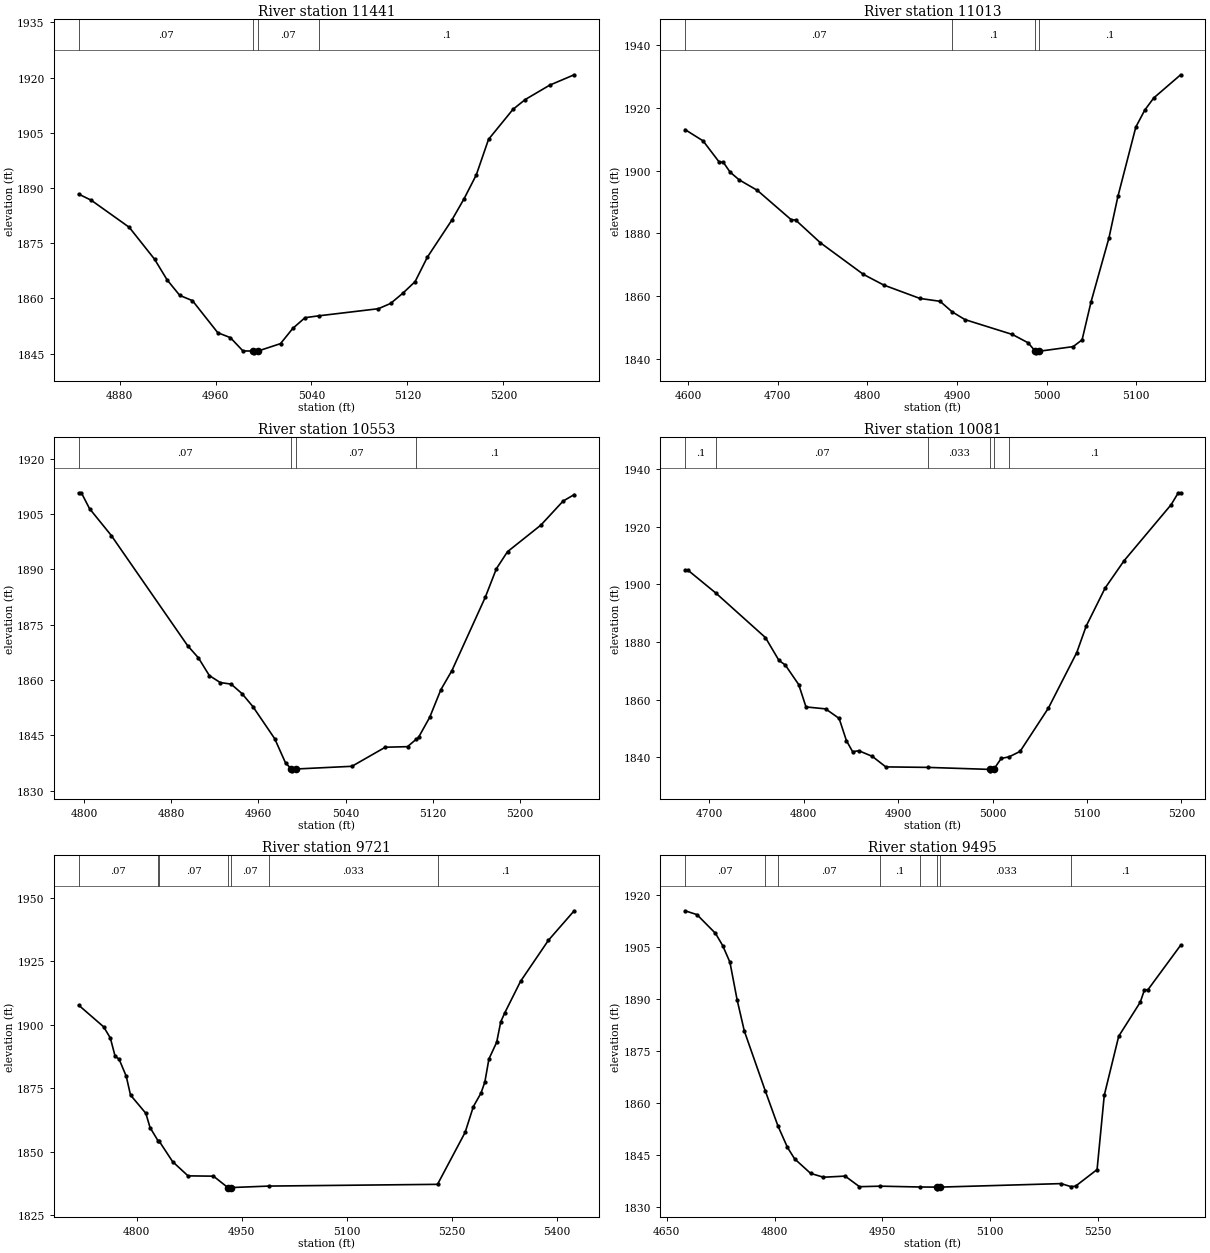
Type RM Length L Ch R = 1,11441,428,428,428
BEGIN DESCRIPTION:
Lin Prong 25.0
END DESCRIPTION:
XS GIS Cut Line= 3
      1906475.00     13876425.01      1906425.00     13876275.00
      1906374.99     13876024.97
#Sta/Elev= 30
  4845.9 1888.34  4856.4 1886.67  4888.1 1879.31  4909.2 1870.64  4919.7 1865.01
  4930.2 1860.81  4940.8 1859.38  4961.9 1850.67  4972.4 1849.33  4982.9 1845.71
  4991.4 1845.70  4991.7 1845.20  4995.5 1845.70  5014.2 1847.70  5024.4 1851.83
  5034.6 1854.75  5046.1 1855.26  5095.8 1857.19  5106.0 1858.63  5116.2 1861.41
  5126.4 1864.55  5136.6 1871.19  5157.0 1881.26  5167.2 1887.06  5177.4 1893.55
  5187.6 1903.21  5208.0 1911.37  5218.2 1914.03  5238.6 1917.94  5259.0 1920.76
#Mann=4,-1,0
  4845.9    0.07       0  4991.4    0.05       0  4995.5    0.07       0
  5046.1     0.1       0
Bank Sta=4991.4,4995.5
Exp/Cntr=0.3,0.1

Type RM Length L Ch R = 1,11013,460,460,460
BEGIN DESCRIPTION:
Lin Prong 24.0
END DESCRIPTION:
XS GIS Cut Line= 3
      1906824.99     13876474.95      1906775.00     13876075.00
      1906775.00     13875924.96
#Sta/Elev= 30
  4596.5 1913.05  4616.6 1909.45  4634.2 1902.85  4639.3 1902.58  4646.8 1899.49
  4656.9 1897.04  4677.1 1893.71  4714.9 1884.36  4719.9 1884.25  4747.6 1876.99
  4795.5 1866.95  4818.2 1863.55  4858.5 1859.29  4881.1 1858.37  4894.6 1855.01
  4908.9 1852.54  4961.8 1847.81  4979.4 1845.15  4987.4 1842.46  4987.7 1841.96
  4991.5 1842.46  5029.6 1843.94  5039.6 1846.09  5049.6 1858.19  5069.6 1878.57
  5079.6 1891.80  5099.6 1913.88  5109.6 1919.28  5119.6 1923.14  5149.6 1930.51
#Mann=4,-1,0
  4596.5    0.07       0  4894.6     0.1       0  4987.4    0.05       0
  4991.5     0.1       0
Bank Sta=4987.4,4991.5
Exp/Cntr=0.3,0.1

Type RM Length L Ch R = 1,10553,472,472,472
BEGIN DESCRIPTION:
Lin Prong 23.0
END DESCRIPTION:
XS GIS Cut Line= 3
      1907175.00     13876424.95      1907175.00     13876225.00
      1907225.00     13875975.00
#Sta/Elev= 30
  4795.0 1910.72  4797.5 1910.72  4805.0 1906.43  4825.0 1899.14  4895.0 1869.31
  4905.0 1865.97  4915.0 1861.18  4925.0 1859.30  4935.0 1858.87  4945.0 1856.29
  4955.0 1852.77  4975.0 1844.08  4985.0 1837.47  4990.4 1835.87  4990.6 1835.37
  4994.6 1835.87  5045.9 1836.60  5076.5 1841.77  5096.9 1841.92  5104.7 1843.88
  5107.1 1844.48  5117.3 1849.89  5127.5 1857.35  5137.7 1862.55  5168.3 1882.41
  5178.5 1890.15  5188.7 1894.76  5219.3 1901.95  5239.7 1908.46  5249.9 1910.22
#Mann=4,-1,0
  4795.0    0.07       0  4990.4    0.05       0  4994.6    0.07       0
  5104.7     0.1       0
Bank Sta=4990.4,4994.6
Exp/Cntr=0.3,0.1

Type RM Length L Ch R = 1,10081,360,360,360
BEGIN DESCRIPTION:
Lin Prong 22.0
END DESCRIPTION:
XS GIS Cut Line= 3
      1907374.98     13876425.02      1907577.70     13876186.98
      1907575.00     13875974.97
#Sta/Elev= 30
  4674.5 1904.85  4677.8 1904.85  4707.0 1897.00  4759.6 1881.51  4773.9 1873.57
  4780.5 1872.03  4794.8 1865.20  4802.5 1857.43  4823.3 1856.75  4837.6 1853.44
  4845.3 1845.72  4851.9 1841.87  4858.4 1842.22  4872.7 1840.26  4887.0 1836.60
  4931.2 1836.43  4997.0 1835.73  4997.3 1835.23  5001.3 1835.73  5009.2 1839.54
  5017.6 1840.09  5029.2 1841.98  5059.2 1857.04  5089.2 1876.31  5099.2 1885.52
  5119.2 1898.71  5139.2 1908.17  5189.2 1927.71  5196.7 1931.82  5199.2 1931.82
#Mann=6,-1,0
  4674.5     0.1       0  4707.0    0.07       0  4931.2   0.033       0
  4997.0   0.033       0  5001.3   0.033       0  5017.6     0.1       0
Bank Sta=4997,5001.3
Exp/Cntr=0.3,0.1

Type RM Length L Ch R = 1,9721,226,226,226
BEGIN DESCRIPTION:
Lin Prong 21.0
END DESCRIPTION:
XS GIS Cut Line= 3
      1907424.98     13876575.01      1907708.72     13876423.84
      1907874.98     13876075.03
#Sta/Elev= 30
  4716.9 1907.75  4752.7 1899.19  4762.2 1894.79  4769.0 1887.64  4774.7 1886.47
  4784.9 1879.76  4791.0 1872.35  4812.9 1865.15  4818.9 1859.56  4830.5 1854.26
  4832.1 1854.13  4851.2 1846.10  4873.2 1840.52  4909.5 1840.40  4930.1 1835.91
  4930.4 1835.41  4934.4 1835.91  4988.9 1836.50  5229.6 1837.18  5269.0 1857.63
  5280.8 1867.80  5291.7 1873.11  5297.2 1877.46  5303.0 1886.54  5314.1 1893.13
  5319.9 1901.17  5325.5 1904.62  5348.2 1917.13  5388.0 1933.28  5424.8 1944.90
#Mann=7,-1,0
  4716.9    0.07       0  4830.5     0.1       0  4832.1    0.07       0
  4930.1   0.033       0  4934.4    0.07       0  4988.9   0.033       0
  5229.6     0.1       0
Bank Sta=4930.1,4934.4
Exp/Cntr=0.3,0.1

Type RM Length L Ch R = 1,9495,101,101,101
BEGIN DESCRIPTION:
Mapping XS ebbbcaa6
END DESCRIPTION:
XS GIS Cut Line= 2
      1907392.76     13876641.01      1908081.05     13876596.81
#Sta/Elev= 30
  4675.5 1915.38  4692.0 1914.27  4717.8 1908.86  4727.8 1905.34  4737.9 1900.53
  4747.9 1889.68  4757.9 1880.69  4787.4 1863.22  4804.7 1853.28  4818.0 1847.06
  4828.0 1843.75  4850.2 1839.57  4868.1 1838.46  4898.2 1838.79  4918.2 1835.73
  4947.4 1835.88  5002.6 1835.64  5026.3 1835.61  5026.6 1835.11  5030.6 1835.61
  5198.8 1836.62  5212.5 1835.75  5218.9 1835.88  5248.9 1840.67  5258.9 1862.11
  5279.0 1879.16  5309.0 1888.99  5314.8 1892.53  5319.8 1892.62  5365.2 1905.43
#Mann=8,-1,0
  4675.5    0.07       0  4787.4     0.1       0  4804.7    0.07       0
  4947.4     0.1       0  5002.6   0.033       0  5026.3    0.05       0
  5030.6   0.033       0  5212.5     0.1       0
Bank Sta=5026.3,5030.6
Exp/Cntr=0.3,0.1

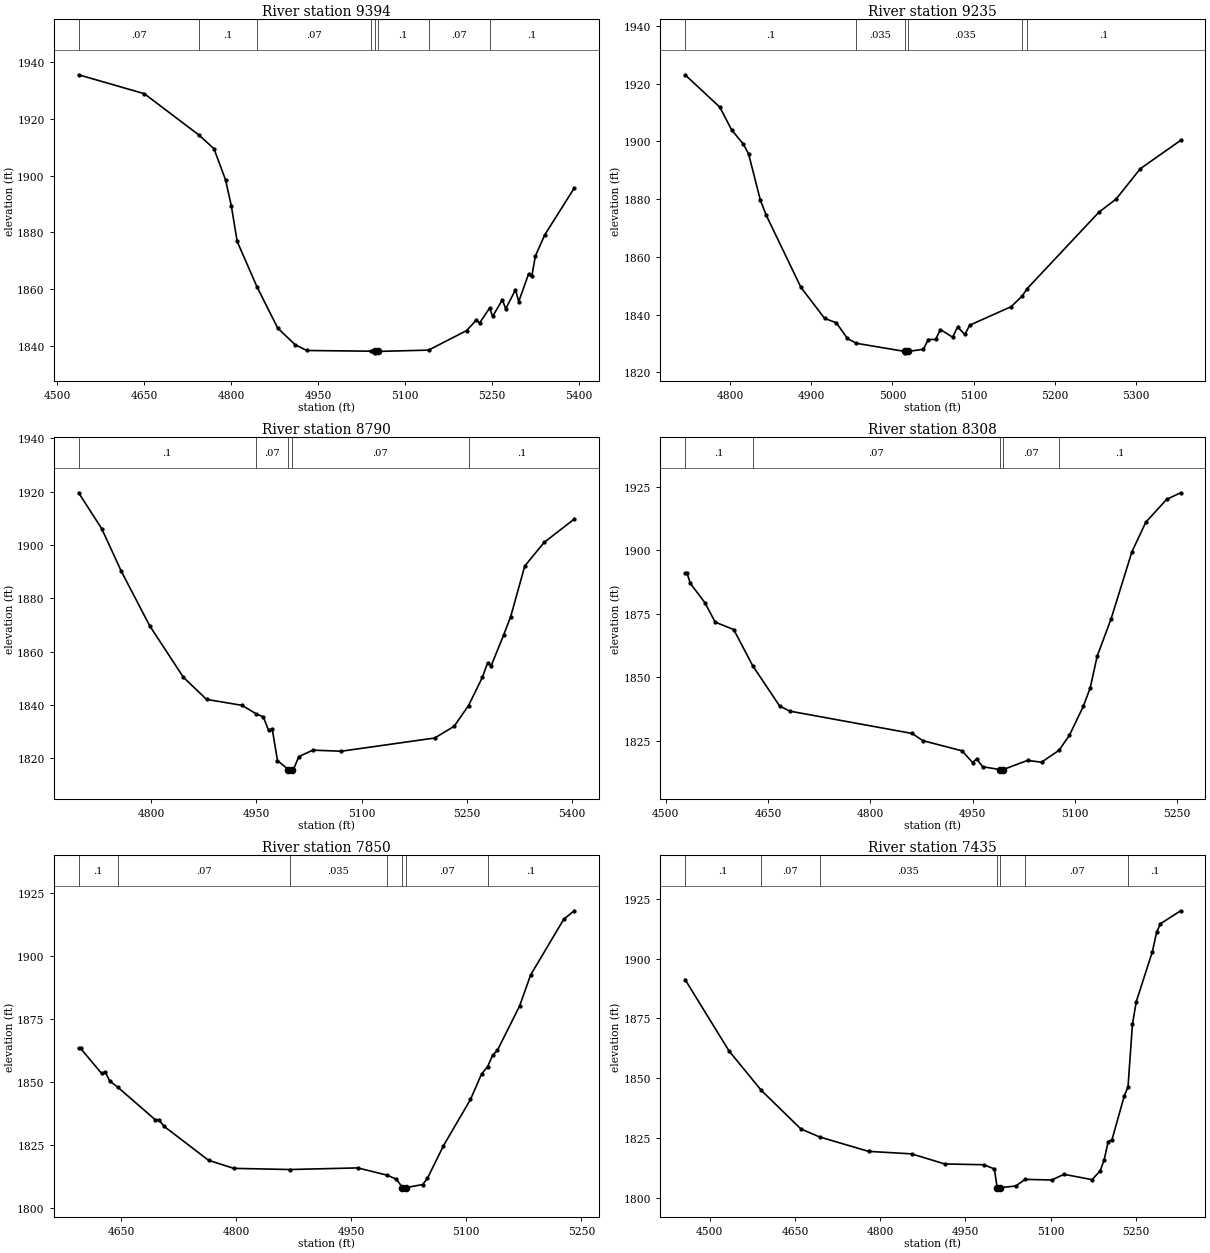
Type RM Length L Ch R = 1,9394,159,159,159
BEGIN DESCRIPTION:
Lin Prong D1
END DESCRIPTION:
XS GIS Cut Line= 4
      1907211.75     13876704.32      1907756.94     13876707.79
      1907861.11     13876707.79      1908045.10     13876617.53
#Sta/Elev= 30
  4536.9 1935.57  4650.1 1928.90  4743.7 1914.41  4770.2 1909.48  4790.2 1898.47
  4800.2 1889.25  4810.2 1876.78  4844.5 1860.68  4880.2 1846.18  4910.2 1840.31
  4930.2 1838.29  5041.5 1838.04  5048.0 1837.96  5048.3 1837.46  5052.4 1837.96
  5140.1 1838.42  5205.6 1845.29  5222.5 1848.99  5228.1 1847.99  5245.5 1853.27
  5250.6 1850.32  5267.5 1856.20  5273.1 1852.95  5290.0 1859.71  5295.6 1855.53
  5312.5 1865.24  5318.1 1864.41  5324.3 1871.62  5340.6 1879.13  5391.2 1895.55
#Mann=8,-1,0
  4536.9    0.07       0  4743.7     0.1       0  4844.5    0.07       0
  5041.5     0.1       0  5048.0    0.05       0  5052.4     0.1       0
  5140.1    0.07       0  5245.5     0.1       0
Bank Sta=5048,5052.4
Exp/Cntr=0.3,0.1

Type RM Length L Ch R = 1,9235,445,445,445
BEGIN DESCRIPTION:
Lin Prong 20.0
END DESCRIPTION:
XS GIS Cut Line= 3
      1907574.97     13876975.02      1907775.00     13876825.00
      1908075.00     13876625.00
#Sta/Elev= 30
  4744.5 1923.05  4787.2 1911.86  4801.8 1903.98  4816.4 1898.98  4822.7 1895.67
  4837.2 1879.66  4844.5 1874.37  4887.2 1849.41  4916.4 1838.67  4931.0 1837.10
  4944.5 1831.69  4955.5 1830.03  5014.9 1827.22  5015.2 1826.72  5019.3 1827.22
  5038.1 1827.94  5044.1 1831.33  5053.1 1831.36  5059.1 1834.80  5074.2 1832.13
  5080.2 1835.69  5089.2 1833.08  5095.2 1836.30  5146.3 1842.72  5160.0 1846.44
  5165.7 1848.88  5254.4 1875.44  5275.5 1879.98  5305.5 1890.53  5355.1 1900.33
#Mann=6,-1,0
  4744.5     0.1       0  4955.5   0.035       0  5014.9   0.035       0
  5019.3   0.035       0  5160.0    0.07       0  5165.7     0.1       0
Bank Sta=5014.9,5019.3
Exp/Cntr=0.3,0.1

Type RM Length L Ch R = 1,8790,482,482,482
BEGIN DESCRIPTION:
Lin Prong 19.0
END DESCRIPTION:
XS GIS Cut Line= 3
      1908075.00     13877324.97      1908125.00     13877025.00
      1908175.00     13876625.02
#Sta/Elev= 30
  4696.3 1919.55  4729.2 1906.12  4757.1 1890.20  4797.7 1869.72  4845.8 1850.43
  4878.8 1842.15  4929.4 1839.91  4949.2 1836.81  4959.9 1835.56  4967.5 1830.49
  4972.5 1831.18  4980.1 1819.22  4995.6 1815.87  4995.9 1815.37  5000.1 1815.87
  5002.9 1815.87  5010.5 1820.71  5030.6 1823.12  5071.0 1822.72  5204.5 1827.67
  5232.2 1832.06  5252.7 1839.84  5272.5 1850.40  5280.1 1855.93  5285.1 1854.78
  5302.7 1866.17  5312.8 1873.05  5333.0 1892.13  5360.7 1900.97  5403.5 1909.68
#Mann=5,-1,0
  4696.3     0.1       0  4949.2    0.07       0  4995.6    0.05       0
  5000.1    0.07       0  5252.7     0.1       0
Bank Sta=4995.6,5000.1
Exp/Cntr=0.3,0.1

Type RM Length L Ch R = 1,8308,458,458,458
BEGIN DESCRIPTION:
Lin Prong 18.0
END DESCRIPTION:
XS GIS Cut Line= 3
      1908325.00     13877325.00      1908575.00     13876925.00
      1908625.01     13876674.95
#Sta/Elev= 30
  4528.3 1890.82  4531.2 1890.82  4536.0 1886.91  4557.2 1879.35  4572.5 1871.64
  4599.6 1868.74  4627.4 1854.51  4666.9 1838.63  4681.6 1836.62  4861.4 1827.81
  4876.8 1825.00  4934.6 1820.96  4949.9 1816.36  4955.8 1817.84  4964.6 1814.72
  4990.1 1813.60  4990.4 1813.10  4994.6 1813.60  5030.6 1817.21  5051.0 1816.50
  5076.6 1821.18  5091.8 1827.05  5112.2 1838.46  5122.4 1845.78  5132.6 1858.23
  5153.0 1872.94  5183.6 1899.38  5204.0 1911.03  5234.6 1920.00  5255.0 1922.58
#Mann=5,-1,0
  4528.3     0.1       0  4627.4    0.07       0  4990.1    0.05       0
  4994.6    0.07       0  5076.6     0.1       0
Bank Sta=4990.1,4994.6
Exp/Cntr=0.3,0.1

Type RM Length L Ch R = 1,7850,415,415,415
BEGIN DESCRIPTION:
Lin Prong 17.0
END DESCRIPTION:
XS GIS Cut Line= 3
      1908925.00     13877275.02      1908991.81     13876820.24
      1908874.97     13876674.96
#Sta/Elev= 30
  4594.5 1863.37  4597.0 1863.37  4624.4 1853.44  4629.4 1853.86  4635.0 1850.44
  4645.8 1847.91  4694.1 1835.17  4699.2 1835.04  4705.7 1832.53  4763.9 1819.03
  4796.7 1815.84  4869.8 1815.38  4958.4 1816.02  4996.6 1813.15  5008.9 1811.54
  5016.7 1808.23  5017.0 1807.73  5021.4 1808.23  5043.0 1809.42  5049.2 1811.85
  5070.2 1824.82  5105.4 1843.11  5119.8 1853.18  5127.8 1856.13  5134.2 1860.58
  5140.6 1862.65  5169.4 1880.08  5183.8 1892.40  5226.9 1914.43  5240.6 1917.83
#Mann=7,-1,0
  4594.5     0.1       0  4645.8    0.07       0  4869.8   0.035       0
  4996.6    0.07       0  5016.7    0.05       0  5021.4    0.07       0
  5127.8     0.1       0
Bank Sta=5016.7,5021.4
Exp/Cntr=0.3,0.1

Type RM Length L Ch R = 1,7435,517,517,517
BEGIN DESCRIPTION:
Lin Prong 16.0
END DESCRIPTION:
XS GIS Cut Line= 3
      1909194.87     13877391.15      1909377.43     13876843.82
      1909575.01     13876624.99
#Sta/Elev= 30
  4456.7 1891.22  4533.9 1861.40  4590.7 1844.90  4660.4 1828.75  4693.3 1825.41
  4779.4 1819.38  4855.3 1818.33  4913.3 1814.12  4981.8 1813.79  5000.8 1812.05
  5005.7 1804.21  5006.1 1803.71  5010.5 1804.21  5038.2 1804.88  5055.1 1807.67
  5101.7 1807.41  5123.3 1809.78  5172.7 1807.55  5186.9 1811.23  5193.8 1815.71
  5201.1 1823.48  5207.8 1824.29  5229.5 1842.73  5235.9 1846.30  5243.7 1872.49
  5250.4 1881.94  5278.8 1902.91  5286.3 1911.06  5293.0 1914.56  5328.5 1919.98
#Mann=7,-1,0
  4456.7     0.1       0  4590.7    0.07       0  4693.3   0.035       0
  5005.7   0.035       0  5010.5   0.035       0  5055.1    0.07       0
  5235.9     0.1       0
Bank Sta=5005.7,5010.5
Exp/Cntr=0.3,0.1

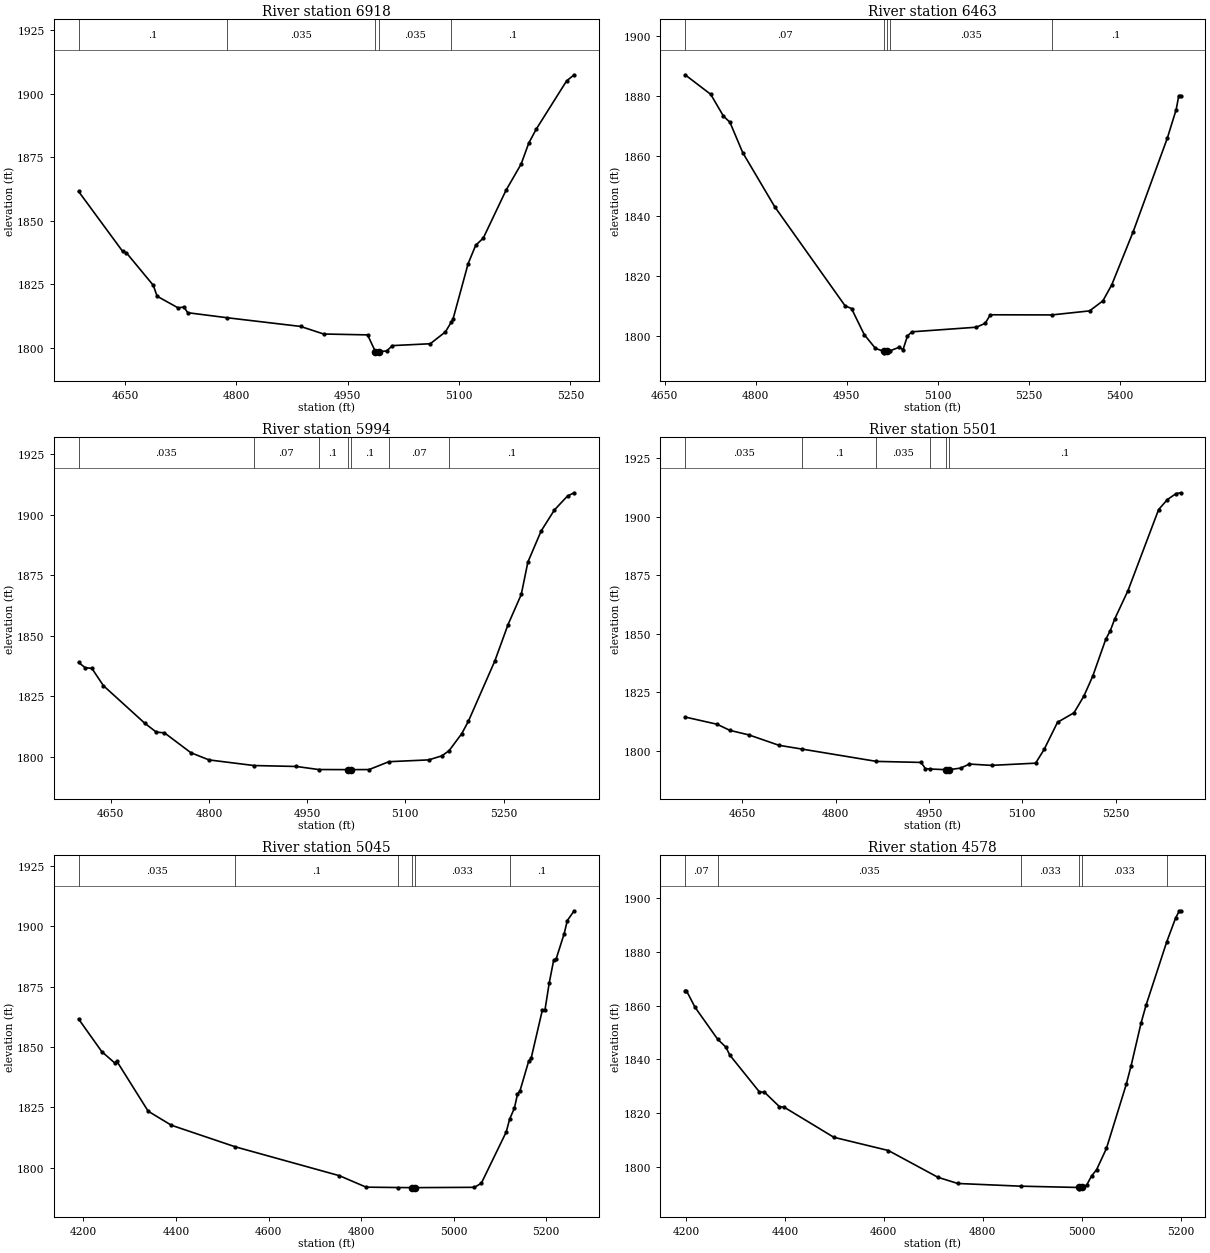
Type RM Length L Ch R = 1,6918,455,455,455
BEGIN DESCRIPTION:
Lin Prong 15.0
END DESCRIPTION:
XS GIS Cut Line= 3
      1909674.99     13877375.02      1909775.00     13876975.00
      1909725.00     13876724.98
#Sta/Elev= 30
  4587.7 1861.46  4647.0 1837.86  4652.1 1837.28  4688.2 1824.52  4693.4 1820.21
  4721.7 1815.61  4729.5 1815.97  4734.6 1813.72  4787.5 1811.74  4886.6 1808.31
  4917.6 1805.33  4976.8 1804.98  4987.3 1798.41  4987.6 1797.91  4992.2 1798.41
  5002.6 1798.66  5010.2 1800.76  5061.2 1801.49  5081.6 1806.15  5089.7 1810.11
  5091.8 1811.14  5112.2 1833.03  5122.4 1840.28  5132.6 1843.10  5163.2 1861.93
  5183.6 1872.28  5193.8 1880.49  5204.0 1886.06  5244.8 1905.02  5255.0 1907.43
#Mann=5,-1,0
  4587.7     0.1       0  4787.5   0.035       0  4987.3   0.035       0
  4992.2   0.035       0  5089.7     0.1       0
Bank Sta=4987.3,4992.2
Exp/Cntr=0.3,0.1

Type RM Length L Ch R = 1,6463,469,469,469
BEGIN DESCRIPTION:
Lin Prong 14.0
END DESCRIPTION:
XS GIS Cut Line= 3
      1910275.00     13877424.99      1910175.00     13877125.00
      1909875.01     13876725.01
#Sta/Elev= 30
  4683.9 1887.15  4726.1 1880.62  4747.1 1873.33  4757.7 1871.31  4778.8 1861.16
  4831.5 1843.08  4947.4 1810.00  4958.0 1809.08  4979.0 1800.37  4997.5 1795.76
  5011.2 1794.79  5011.6 1794.29  5016.2 1794.79  5020.6 1794.90  5036.6 1796.16
  5042.8 1795.32  5050.1 1799.90  5057.4 1801.31  5163.7 1802.85  5178.2 1804.15
  5186.6 1807.00  5287.7 1806.95  5350.1 1808.30  5372.0 1811.64  5386.6 1816.98
  5422.0 1834.78  5478.2 1866.01  5492.8 1875.55  5497.0 1880.17  5500.1 1880.17
#Mann=5,-1,0
  4683.9    0.07       0  5011.2    0.05       0  5016.2    0.07       0
  5020.6   0.035       0  5287.7     0.1       0
Bank Sta=5011.2,5016.2
Exp/Cntr=0.3,0.1

Type RM Length L Ch R = 1,5994,493,493,493
BEGIN DESCRIPTION:
Lin Prong 13.0
END DESCRIPTION:
XS GIS Cut Line= 3
      1910474.99     13877275.04      1910525.00     13876875.00
      1910475.00     13876525.01
#Sta/Elev= 30
  4601.1 1839.03  4611.2 1836.86  4621.3 1836.62  4638.9 1829.47  4701.9 1814.00
  4719.6 1810.30  4732.2 1809.98  4772.5 1801.78  4800.2 1798.81  4868.8 1796.49
  4933.7 1796.10  4967.5 1794.84  5011.9 1794.80  5012.2 1794.30  5016.9 1794.80
  5044.7 1794.83  5074.8 1798.07  5135.6 1798.82  5155.8 1800.49  5166.8 1802.63
  5186.1 1809.64  5196.2 1814.74  5236.6 1839.63  5256.8 1854.66  5277.0 1867.11
  5287.1 1880.47  5307.3 1893.28  5327.5 1901.95  5347.7 1907.78  5357.8 1909.09
#Mann=7,-1,0
  4601.1   0.035       0  4868.8    0.07       0  4967.5     0.1       0
  5011.9    0.05       0  5016.9     0.1       0  5074.8    0.07       0
  5166.8     0.1       0
Bank Sta=5011.9,5016.9
Exp/Cntr=0.3,0.1

Type RM Length L Ch R = 1,5501,456,456,456
BEGIN DESCRIPTION:
Lin Prong 12.0
END DESCRIPTION:
XS GIS Cut Line= 3
      1910975.00     13877125.00      1910892.54     13876773.29
      1910575.01     13876475.01
#Sta/Elev= 30
  4557.8 1814.42  4609.2 1811.34  4629.7 1808.74  4660.5 1806.78  4708.9 1802.34
  4746.2 1800.72  4865.6 1795.48  4937.4 1795.04  4944.2 1792.40  4951.8 1792.23
  4977.2 1791.95  4977.6 1791.45  4982.5 1791.95  5000.9 1792.62  5015.0 1794.34
  5050.7 1793.78  5121.5 1794.73  5135.2 1800.60  5156.7 1812.17  5183.2 1816.23
  5199.1 1823.35  5213.3 1831.83  5234.3 1847.63  5241.6 1851.27  5248.5 1856.16
  5270.0 1868.36  5319.3 1902.98  5333.5 1907.27  5347.6 1909.83  5354.7 1910.14
#Mann=6,-1,0
  4557.8   0.035       0  4746.2     0.1       0  4865.6   0.035       0
  4951.8     0.1       0  4977.2    0.05       0  4982.5     0.1       0
Bank Sta=4977.2,4982.5
Exp/Cntr=0.3,0.1

Type RM Length L Ch R = 1,5045,467,467,467
BEGIN DESCRIPTION:
Lin Prong 11.0
END DESCRIPTION:
XS GIS Cut Line= 3
      1911075.00     13877325.01      1911125.00     13876525.00
      1911025.01     13876275.03
#Sta/Elev= 30
  4189.7 1861.54  4239.8 1848.03  4267.4 1843.42  4272.4 1844.03  4340.0 1823.36
  4390.1 1817.56  4528.0 1808.63  4753.3 1796.65  4810.9 1791.91  4880.7 1791.75
  4911.0 1791.71  4911.4 1791.21  4916.3 1791.71  5045.1 1791.84  5059.9 1793.54
  5113.8 1814.81  5120.9 1820.02  5131.3 1824.63  5138.0 1830.38  5143.4 1831.80
  5162.3 1844.17  5167.6 1845.35  5191.9 1865.40  5197.3 1865.21  5206.7 1876.62
  5216.1 1885.82  5221.5 1886.43  5239.0 1896.97  5245.7 1902.37  5260.5 1906.40
#Mann=6,-1,0
  4189.7   0.035       0  4528.0     0.1       0  4880.7   0.033       0
  4911.0   0.033       0  4916.3   0.033       0  5120.9     0.1       0
Bank Sta=4911,4916.3
Exp/Cntr=0.3,0.1

Type RM Length L Ch R = 1,4578,483,483,483
BEGIN DESCRIPTION:
Lin Prong 10.0
END DESCRIPTION:
XS GIS Cut Line= 3
      1911475.00     13877325.03      1911525.00     13876525.00
      1911525.00     13876324.99
#Sta/Elev= 30
  4198.3 1865.59  4200.8 1865.59  4218.4 1859.37  4263.9 1847.57  4281.0 1844.53
  4288.5 1841.66  4348.6 1827.94  4358.6 1827.87  4388.7 1822.54  4398.7 1822.26
  4498.9 1811.12  4609.1 1806.21  4709.3 1796.27  4749.4 1793.97  4876.6 1792.97
  4994.7 1792.48  4995.1 1791.98  5000.1 1792.48  5009.9 1793.35  5019.9 1796.78
  5029.9 1799.04  5049.9 1806.97  5089.9 1830.72  5099.9 1837.76  5119.9 1853.53
  5129.9 1860.10  5171.7 1883.62  5189.9 1892.59  5197.4 1895.20  5199.9 1895.20
#Mann=6,-1,0
  4198.3    0.07       0  4263.9   0.035       0  4876.6   0.033       0
  4994.7   0.033       0  5000.1   0.033       0  5171.7     0.1       0
Bank Sta=4994.7,5000.1
Exp/Cntr=0.3,0.1

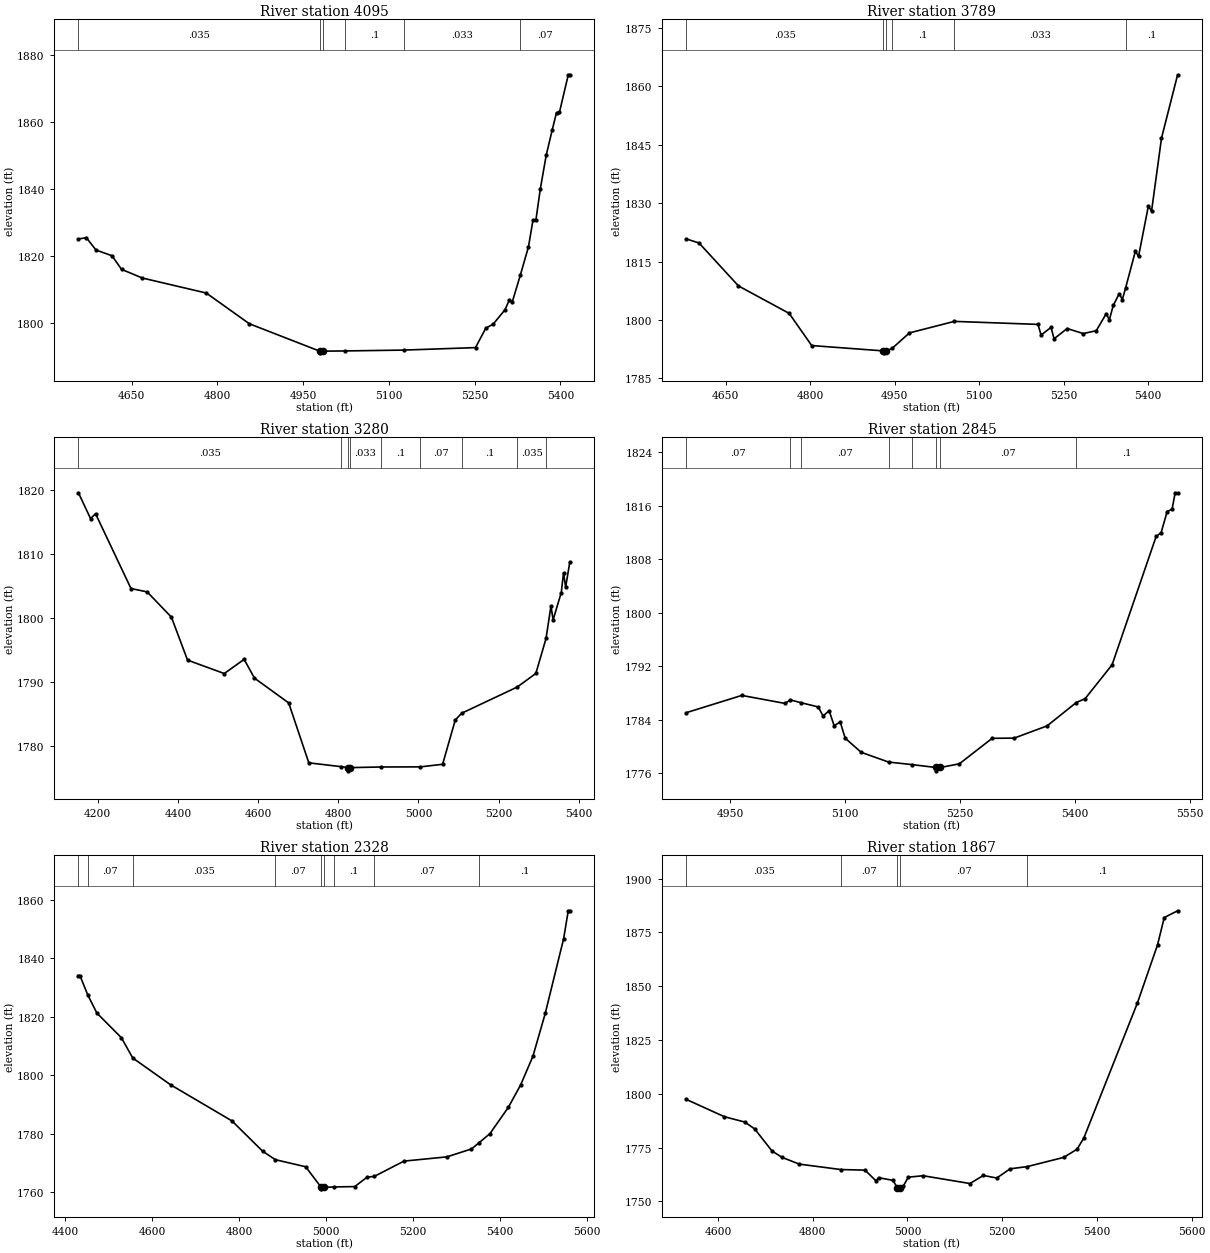
Type RM Length L Ch R = 1,4095,306,306,306
BEGIN DESCRIPTION:
Lin Prong 9.0
END DESCRIPTION:
XS GIS Cut Line= 3
      1911625.02     13877174.97      1911825.00     13876775.00
      1911725.00     13876374.99
#Sta/Elev= 30
  4557.0 1825.22  4570.9 1825.60  4587.7 1821.92  4615.7 1820.22  4632.4 1816.16
  4668.8 1813.57  4780.6 1809.09  4856.0 1799.92  4979.1 1791.74  4979.5 1791.24
  4984.5 1791.74  5023.6 1791.81  5125.9 1792.06  5251.6 1792.80  5269.6 1798.60
  5282.5 1799.81  5303.1 1804.07  5310.8 1807.02  5316.0 1806.47  5330.3 1814.59
  5344.3 1822.93  5352.1 1830.80  5357.2 1830.79  5364.9 1840.07  5375.3 1850.23
  5385.6 1857.62  5393.3 1862.94  5398.4 1862.99  5413.9 1874.22  5416.5 1874.22
#Mann=6,-1,0
  4557.0   0.035       0  4979.1   0.035       0  4984.5   0.035       0
  5023.6     0.1       0  5125.9   0.033       0  5330.3    0.07       0
Bank Sta=4979.1,4984.5
Exp/Cntr=0.3,0.1

Type RM Length L Ch R = 1,3789,509,509,509
BEGIN DESCRIPTION:
Mapping XS 6fb43e09
END DESCRIPTION:
XS GIS Cut Line= 3
      1912082.96     13877197.67      1912091.00     13876840.17
      1911879.67     13876370.74
#Sta/Elev= 30
  4579.9 1820.81  4602.6 1819.76  4672.6 1808.73  4762.6 1801.68  4802.6 1793.41
  4929.9 1792.04  4930.3 1791.54  4935.3 1792.04  4945.4 1792.68  4976.1 1796.66
  5055.9 1799.62  5204.4 1798.85  5209.9 1796.11  5227.5 1798.07  5233.0 1795.16
  5256.2 1797.79  5284.8 1796.49  5307.9 1797.23  5325.6 1801.61  5331.1 1800.00
  5338.0 1803.71  5348.7 1806.75  5354.2 1805.24  5360.0 1808.23  5377.4 1817.69
  5382.9 1816.30  5400.5 1829.34  5406.0 1827.90  5423.7 1846.69  5452.3 1862.98
#Mann=6,-1,0
  4579.9   0.035       0  4929.9    0.05       0  4935.3   0.035       0
  4945.4     0.1       0  5055.9   0.033       0  5360.0     0.1       0
Bank Sta=4929.9,4935.3
Exp/Cntr=0.3,0.1

Type RM Length L Ch R = 1,3280,435,435,435
BEGIN DESCRIPTION:
Lin Prong 7.0
END DESCRIPTION:
XS GIS Cut Line= 3
      1912225.00     13877225.04      1912335.72     13876347.00
      1912225.00     13876024.99
#Sta/Elev= 30
  4151.8 1819.54  4182.1 1815.51  4194.5 1816.28  4282.9 1804.61  4323.2 1804.09
  4383.7 1800.15  4424.0 1793.45  4515.6 1791.36  4565.1 1793.57  4590.9 1790.64
  4676.2 1786.78  4726.4 1777.44  4807.1 1776.84  4823.9 1776.69  4824.3 1776.19
  4829.5 1776.69  4905.9 1776.79  5004.7 1776.81  5060.1 1777.21  5091.8 1784.13
  5107.7 1785.17  5246.1 1789.25  5292.7 1791.37  5318.1 1796.83  5330.4 1801.89
  5335.7 1799.72  5356.1 1803.99  5361.7 1807.07  5367.0 1804.83  5377.3 1808.71
#Mann=9,-1,0
  4151.8   0.035       0  4807.1   0.033       0  4823.9    0.05       0
  4829.5   0.033       0  4905.9     0.1       0  5004.7    0.07       0
  5107.7     0.1       0  5246.1   0.035       0  5318.1     0.1       0
Bank Sta=4823.9,4829.5
Exp/Cntr=0.3,0.1

Type RM Length L Ch R = 1,2845,517,517,517
BEGIN DESCRIPTION:
Lin Prong 6.0
END DESCRIPTION:
XS GIS Cut Line= 3
      1912674.99     13876524.99      1912627.45     13876454.75
      1912275.01     13876025.01
#Sta/Elev= 30
  4893.0 1785.07  4965.4 1787.65  5021.9 1786.45  5028.6 1786.98  5043.0 1786.55
  5065.0 1785.93  5071.4 1784.58  5079.3 1785.37  5085.8 1783.12  5093.7 1783.69
  5100.2 1781.26  5121.0 1779.15  5156.8 1777.69  5186.8 1777.32  5218.6 1776.88
  5219.1 1776.38  5224.3 1776.88  5249.1 1777.43  5291.8 1781.24  5320.5 1781.27
  5363.5 1783.10  5401.5 1786.59  5413.0 1787.16  5448.2 1792.23  5505.6 1811.40
  5512.1 1811.98  5520.0 1815.13  5526.4 1815.48  5530.4 1817.93  5533.6 1817.93
#Mann=8,-1,0
  4893.0    0.07       0  5028.6   0.033       0  5043.0    0.07       0
  5156.8   0.033       0  5186.8    0.07       0  5218.6    0.05       0
  5224.3    0.07       0  5401.5     0.1       0
Bank Sta=5218.6,5224.3
Exp/Cntr=0.3,0.1

Type RM Length L Ch R = 1,2328,461,461,461
BEGIN DESCRIPTION:
Lin Prong 5.0
END DESCRIPTION:
XS GIS Cut Line= 3
      1913374.96     13876524.96      1912975.00     13876125.00
      1912575.01     13875725.01
#Sta/Elev= 30
  4430.1 1834.10  4433.6 1834.10  4451.2 1827.60  4472.5 1821.27  4529.0 1812.82
  4555.2 1805.87  4642.2 1796.71  4783.6 1784.33  4854.3 1773.95  4883.6 1771.05
  4953.3 1768.63  4989.2 1761.57  4989.7 1761.07  4995.1 1761.57  5018.6 1761.72
  5066.4 1761.84  5094.7 1765.07  5111.3 1765.33  5179.6 1770.56  5278.6 1772.02
  5335.1 1774.73  5352.1 1776.80  5377.6 1779.97  5420.0 1788.99  5448.3 1796.65
  5476.6 1806.49  5504.9 1821.13  5547.3 1846.75  5557.9 1856.28  5561.4 1856.28
#Mann=9,-1,0
  4430.1     0.1       0  4451.2    0.07       0  4555.2   0.035       0
  4883.6    0.07       0  4989.2    0.05       0  4995.1    0.07       0
  5018.6     0.1       0  5111.3    0.07       0  5352.1     0.1       0
Bank Sta=4989.2,4995.1
Exp/Cntr=0.3,0.1

Type RM Length L Ch R = 1,1867,457,457,457
BEGIN DESCRIPTION:
Lin Prong 4.0
END DESCRIPTION:
XS GIS Cut Line= 3
      1913424.98     13876224.97      1913175.00     13875825.00
      1912775.03     13875425.03
#Sta/Elev= 30
  4533.1 1797.38  4613.8 1789.32  4656.3 1786.88  4677.5 1783.69  4714.1 1773.41
  4735.3 1770.44  4771.9 1767.30  4859.6 1764.78  4910.4 1764.52  4933.4 1759.59
  4939.3 1761.00  4969.4 1759.77  4978.8 1756.32  4979.3 1755.82  4984.7 1756.32
  4991.2 1757.04  5001.8 1761.24  5033.0 1761.91  5132.0 1758.29  5160.3 1762.04
  5188.6 1760.84  5216.9 1765.13  5252.8 1766.15  5330.0 1770.43  5358.3 1774.26
  5372.5 1779.48  5485.6 1842.22  5528.0 1869.18  5542.2 1881.88  5570.4 1885.03
#Mann=5,-1,0
  4533.1   0.035       0  4859.6    0.07       0  4978.8    0.05       0
  4984.7    0.07       0  5252.8     0.1       0
Bank Sta=4978.8,4984.7
Exp/Cntr=0.3,0.1

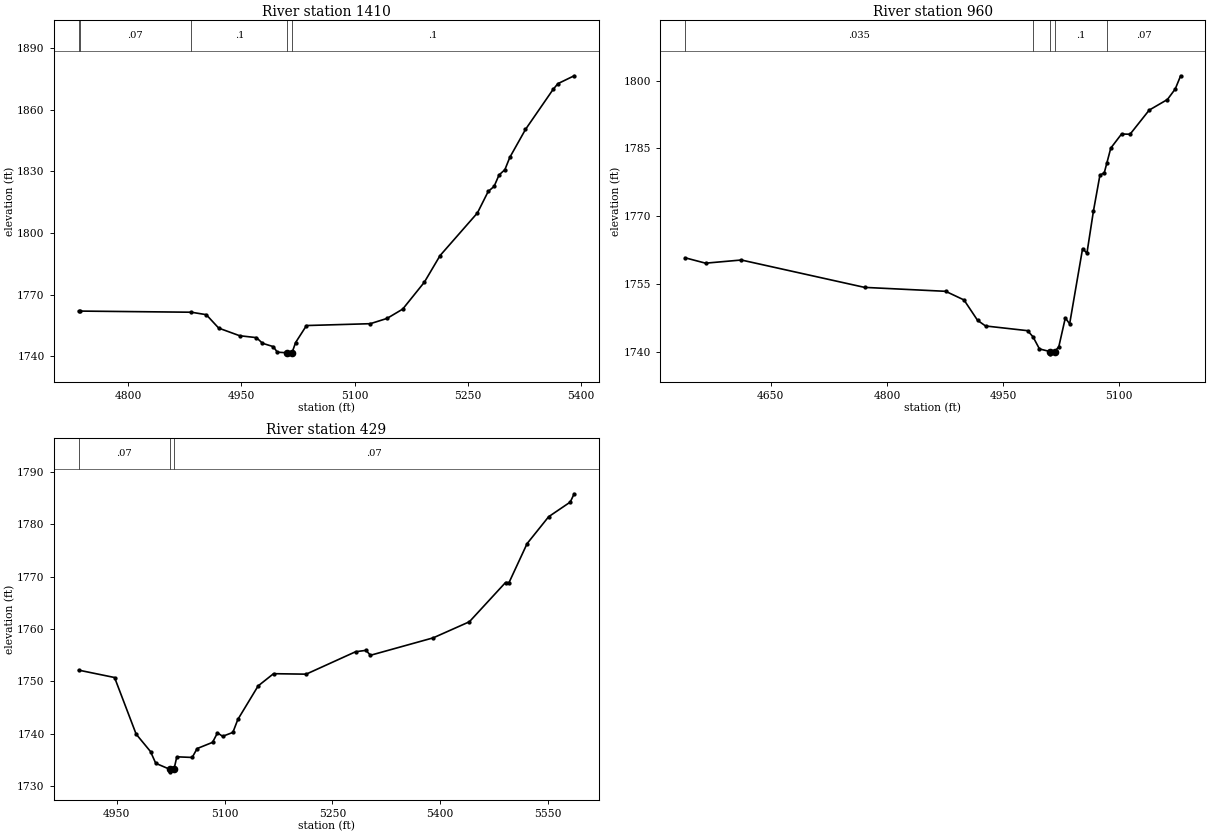
Type RM Length L Ch R = 1,1410,450,450,450
BEGIN DESCRIPTION:
Lin Prong 3.0
END DESCRIPTION:
XS GIS Cut Line= 3
      1913561.58     13875596.73      1913325.00     13875475.00
      1913024.98     13875224.98
#Sta/Elev= 30
  4734.2 1761.89  4735.4 1761.95  4883.5 1761.39  4903.3 1760.20  4919.8 1753.65
  4947.6 1749.93  4969.8 1749.01  4977.8 1746.26  4992.0 1744.64  4997.5 1741.92
  5010.9 1741.61  5011.4 1741.11  5016.9 1741.61  5021.7 1746.62  5036.1 1754.90
  5120.7 1755.80  5142.8 1758.37  5163.6 1762.91  5192.3 1776.03  5213.1 1788.99
  5262.6 1809.77  5276.9 1820.25  5284.7 1822.70  5291.2 1828.24  5299.0 1830.86
  5305.5 1836.84  5326.3 1850.47  5362.8 1869.93  5369.3 1872.79  5390.8 1876.61
#Mann=5,-1,0
  4734.2   0.035       0  4735.4    0.07       0  4883.5     0.1       0
  5010.9    0.05       0  5016.9     0.1       0
Bank Sta=5010.9,5016.9
Exp/Cntr=0.3,0.1

Type RM Length L Ch R = 1,960,531,531,531
BEGIN DESCRIPTION:
Lin Prong 2.0
END DESCRIPTION:
XS GIS Cut Line= 4
      1913637.59     13875571.14      1913525.00     13875125.00
      1913475.00     13875025.00      1913408.13     13875013.37
#Sta/Elev= 30
  4539.4 1760.83  4565.8 1759.64  4612.0 1760.34  4771.1 1754.29  4875.8 1753.42
  4899.5 1751.51  4917.0 1747.01  4927.3 1745.76  4981.6 1744.72  4988.6 1743.36
  4996.9 1740.69  5010.5 1740.10  5011.0 1739.60  5016.5 1740.10  5021.9 1741.17
  5030.3 1747.53  5035.9 1746.23  5052.6 1762.86  5058.2 1761.84  5066.6 1771.15
  5075.0 1779.10  5080.6 1779.61  5083.8 1781.69  5089.0 1785.07  5102.9 1788.19
  5113.9 1788.14  5138.6 1793.47  5162.1 1795.81  5172.2 1798.13  5179.2 1801.06
#Mann=5,-1,0
  4539.4   0.035       0  4988.6     0.1       0  5010.5    0.05       0
  5016.5     0.1       0  5083.8    0.07       0
Bank Sta=5010.5,5016.5
Exp/Cntr=0.3,0.1

Type RM Length L Ch R = 1,429,0,0,0
BEGIN DESCRIPTION:
Lin Prong 1.0
END DESCRIPTION:
XS GIS Cut Line= 6
      1914025.00     13875324.98      1914022.91     13875215.46
      1913875.00     13875075.00      1913798.51     13875017.16
      1913610.08     13874996.72      1913519.54     13874998.43
#Sta/Elev= 30
  4897.0 1752.13  4947.0 1750.72  4977.0 1739.91  4997.0 1736.58  5004.3 1734.33
  5023.6 1733.20  5024.1 1732.70  5029.7 1733.20  5033.6 1735.57  5055.0 1735.45
  5061.9 1737.15  5083.3 1738.33  5090.2 1740.14  5097.4 1739.49  5111.6 1740.23
  5118.5 1742.70  5146.8 1749.12  5168.2 1751.45  5213.6 1751.36  5282.3 1755.64
  5296.8 1755.91  5303.1 1754.97  5390.4 1758.30  5440.7 1761.37  5491.0 1768.87
  5495.9 1768.87  5521.0 1776.30  5551.0 1781.44  5581.0 1784.23  5586.5 1785.82
#Mann=3,-1,0
  4897.0    0.07       0  5023.6    0.05       0  5029.7    0.07       0
Bank Sta=5023.6,5029.7
Exp/Cntr=0.3,0.1

Chan Stop Cuts=-1