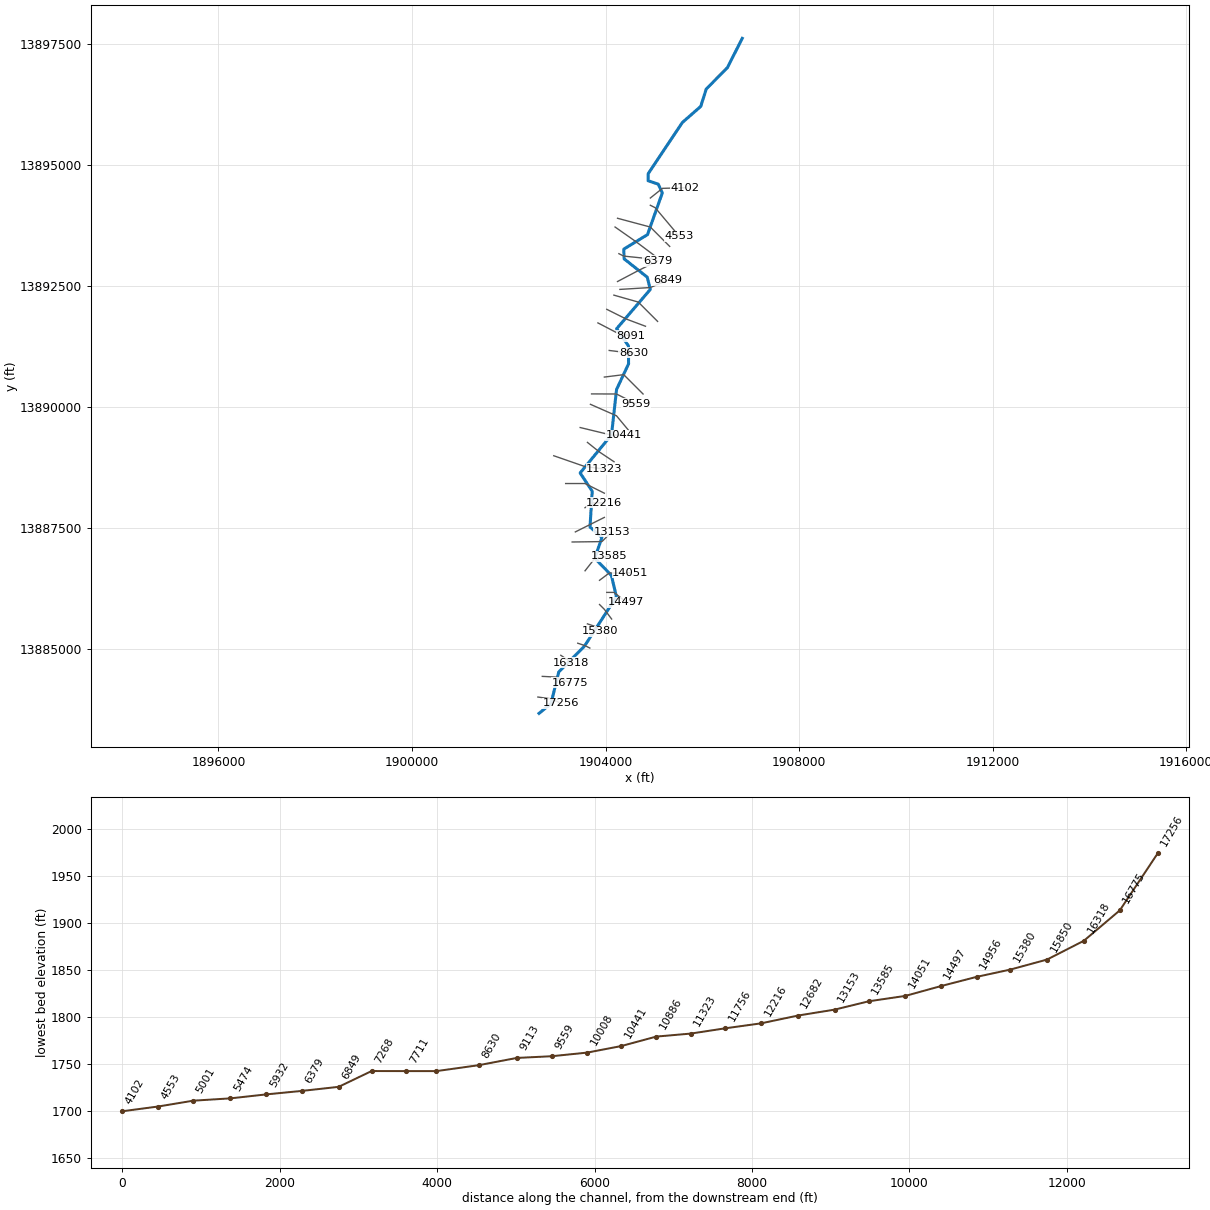
--- Little Lamb Creek.prj (project) ---

Proj Title=Little Lamb Creek Base Level Engineering
Current Plan=p01
Default Exp/Contr=0.3,0.1
English Units
Geom File=g01
Flow File=f01
Plan File=p01
BEGIN DESCRIPTION:
Little Lamb Creek
END DESCRIPTION:

--- Little Lamb Creek.p01 (plan) ---

Plan Title=Multiple Run
Short Identifier=Multiple
Geom File=g01
Flow File=f01
Subcritical Flow
K Sum by GR= 0
Std Step Tol= 0.01
Critical Tol= 0.01
Num of Std Step Trials= 20
Max Error Tol= 0.3
Flow Tol Ratio= 0.001
Split Flow NTrial= 30
Split Flow Tol= 0.02
Split Flow Ratio= 0.02
Log Output Level= 0
Friction Slope Method= 1
Unsteady Friction Slope Method= 2
Unsteady Bridges Friction Slope Method= 1
Parabolic Critical Depth
Global Vel Dist=  1 , 1 , 1
Global Log Level= 0
CheckData=True
Encroach Param= -1, 0, 0, 0
BEGIN DESCRIPTION:
Multiple Run
END DESCRIPTION:

--- Little Lamb Creek.f01 (steady flow) ---

Flow Title=Multiple
Number of Profiles=7
Profile Names=10-year,25-year,50-year,1pct_min,100-year,1pct_plu,500-year
River Rch & RM= Little Lamb Cree,Reach-1,17256
     351     551     727     467     932    1860    1504
River Rch & RM= Little Lamb Cree,Reach-1,16318
    1873    3288    4678    3218    6420   12809   11934
River Rch & RM= Little Lamb Cree,Reach-1,11756
    2684    4807    6926    4815    9606   19167   18264
River Rch & RM= Little Lamb Cree,Reach-1,6849
    3122    5605    8088    5625   11223   22393   21365
Boundary for River Rch & Prof#=Little Lamb Cree,Reach-1,1
Up Type=0
Dn Type=3
Dn Slope=0.005
Boundary for River Rch & Prof#=Little Lamb Cree,Reach-1,2
Up Type=0
Dn Type=3
Dn Slope=0.005
Boundary for River Rch & Prof#=Little Lamb Cree,Reach-1,3
Up Type=0
Dn Type=3
Dn Slope=0.005
Boundary for River Rch & Prof#=Little Lamb Cree,Reach-1,4
Up Type=0
Dn Type=3
Dn Slope=0.005
Boundary for River Rch & Prof#=Little Lamb Cree,Reach-1,5
Up Type=0
Dn Type=3
Dn Slope=0.005
Boundary for River Rch & Prof#=Little Lamb Cree,Reach-1,6
Up Type=0
Dn Type=3
Dn Slope=0.005
Boundary for River Rch & Prof#=Little Lamb Cree,Reach-1,7
Up Type=0
Dn Type=3
Dn Slope=0.005

--- Little Lamb Creek.g01 (geometry) ---

Geom Title=Existing Conditions

River Reach=Little Lamb Cree,Reach-1
Reach XY= 30
      1902625.00     13883675.00      1902871.46     13883876.47
      1903033.16     13884531.05      1903564.23     13885065.30
      1904224.25     13886084.78      1904119.64     13886527.70
      1903777.05     13886880.84      1903924.49     13887309.10
      1903678.53     13887526.46      1903723.80     13888265.41
      1903474.28     13888643.27      1904122.64     13889430.52
      1904227.26     13890369.06      1904475.11     13890897.68
      1904472.83     13891269.56      1904228.44     13891623.74
      1904923.96     13892435.44      1904861.39     13892688.24
      1904382.81     13893068.81      1904377.06     13893269.15
      1904866.86     13893568.94      1905172.72     13894430.57
      1905088.24     13894611.39      1904878.08     13894682.68
      1904880.45     13894827.44      1905585.77     13895884.70
      1905967.14     13896218.83      1906080.42     13896577.67
      1906517.18     13897018.81      1906825.00     13897625.00

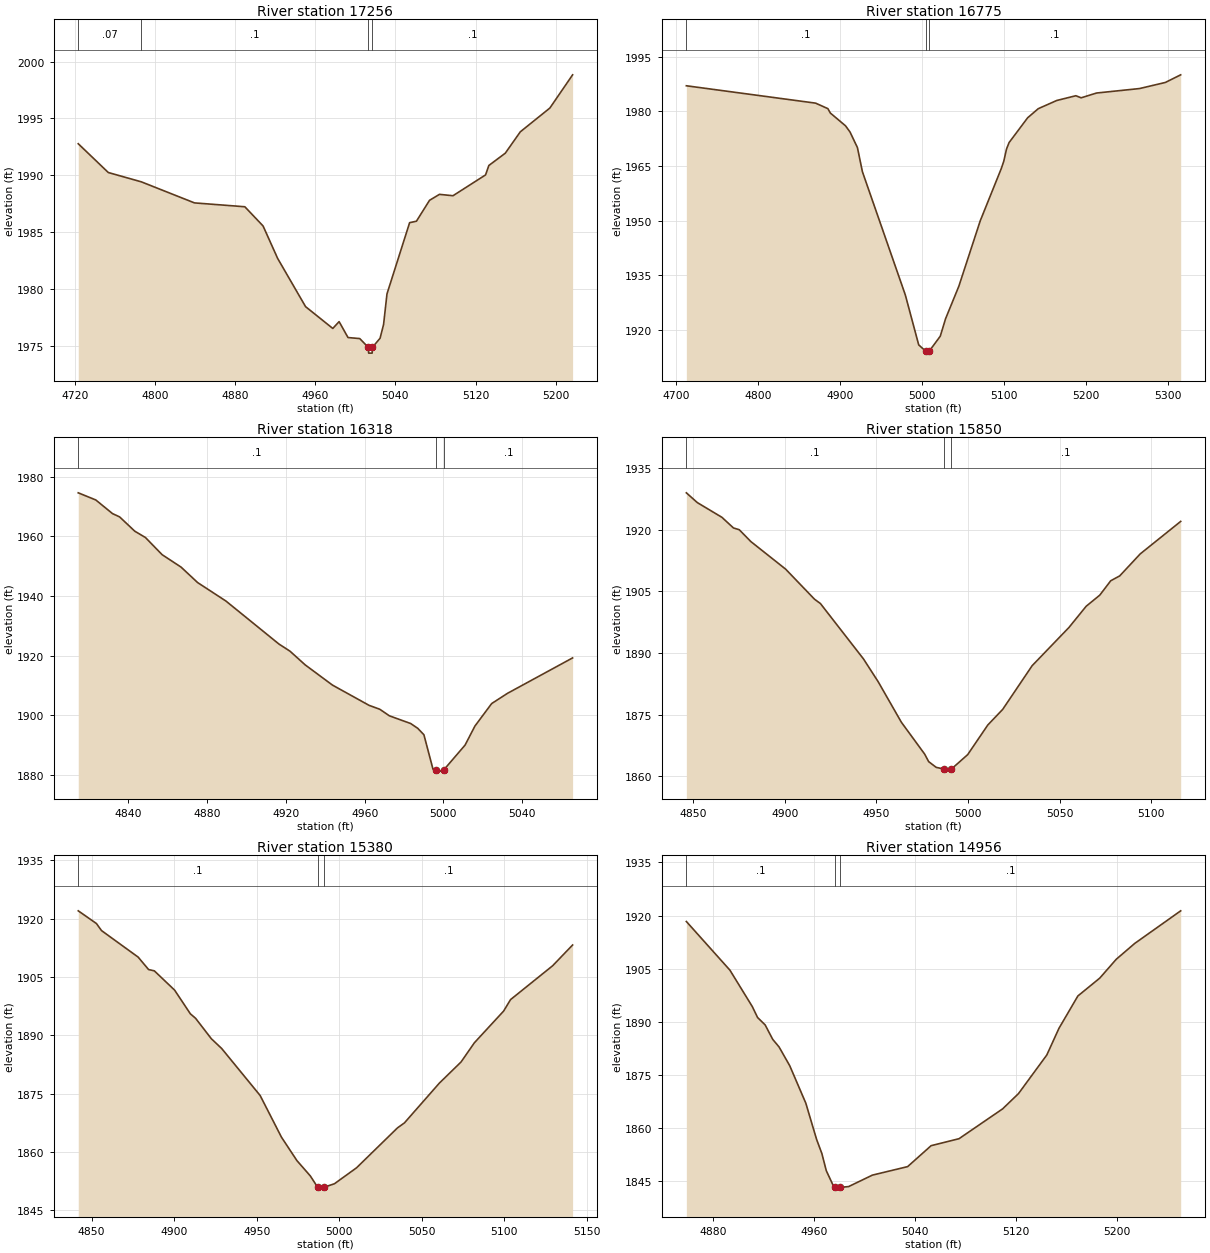
Type RM Length L Ch R = 1,17256,481,481,481
BEGIN DESCRIPTION:
Little Lamb Creek 37.0
END DESCRIPTION:
XS GIS Cut Line= 3
      1902600.66     13884012.80      1902875.00     13883975.00
      1903072.82     13883886.86
#Sta/Elev= 30
  4723.4 1992.77  4753.4 1990.24  4786.4 1989.42  4839.4 1987.57  4889.7 1987.23
  4907.9 1985.54  4922.5 1982.68  4950.3 1978.45  4977.5 1976.53  4983.8 1977.13
  4992.7 1975.73  5004.4 1975.64  5013.0 1974.86  5013.3 1974.36  5016.8 1974.36
  5017.0 1974.86  5024.7 1975.67  5028.2 1976.88  5031.6 1979.57  5054.2 1985.83
  5061.0 1985.96  5074.1 1987.80  5084.0 1988.32  5097.5 1988.20  5130.0 1990.03
  5133.3 1990.86  5149.7 1991.94  5164.7 1993.82  5194.2 1995.91  5216.9 1998.83
#Mann=4,-1,0
  4723.4    0.07       0  4786.4     0.1       0  5013.0    0.05       0
  5017.0     0.1       0
Bank Sta=5013,5017
Exp/Cntr=0.3,0.1

Type RM Length L Ch R = 1,16775,457,457,457
BEGIN DESCRIPTION:
Little Lamb Creek 36.0
END DESCRIPTION:
XS GIS Cut Line= 3
      1902692.15     13884439.74      1902975.00     13884425.00
      1903271.81     13884307.40
#Sta/Elev= 30
  4712.7 1986.99  4870.2 1982.23  4885.2 1980.72  4888.2 1979.52  4906.7 1976.01
  4912.2 1974.31  4921.2 1970.05  4927.3 1963.42  4979.6 1929.64  4995.9 1915.96
  5004.6 1914.20  5004.8 1913.70  5008.6 1914.20  5022.2 1918.35  5028.6 1923.11
  5044.8 1932.03  5070.9 1949.98  5096.6 1964.33  5099.6 1966.33  5102.9 1969.64
  5106.1 1971.44  5128.7 1978.22  5141.6 1980.71  5164.2 1982.96  5187.4 1984.26
  5193.9 1983.69  5212.6 1985.00  5265.1 1986.23  5296.5 1987.90  5315.2 1989.99
#Mann=3,-1,0
  4712.7     0.1       0  5004.6    0.05       0  5008.6     0.1       0
Bank Sta=5004.6,5008.6
Exp/Cntr=0.3,0.1

Type RM Length L Ch R = 1,16318,468,468,468
BEGIN DESCRIPTION:
Little Lamb Creek 35.0
END DESCRIPTION:
XS GIS Cut Line= 3
      1903074.97     13884875.02      1903225.00     13884775.00
      1903274.98     13884725.02
#Sta/Elev= 30
  4814.6 1974.58  4823.5 1972.19  4832.0 1967.61  4835.6 1966.51  4843.3 1961.71
  4848.7 1959.60  4857.2 1953.83  4866.8 1949.67  4875.2 1944.49  4889.6 1938.28
  4916.5 1923.87  4922.1 1921.48  4929.8 1916.89  4943.7 1910.09  4962.3 1903.30
  4967.7 1902.00  4972.6 1899.79  4983.4 1897.21  4987.0 1895.59  4990.1 1893.45
  4994.7 1881.94  4996.3 1881.75  4996.6 1881.25  5000.1 1881.25  5000.3 1881.75
  5011.0 1889.98  5016.0 1896.36  5024.5 1903.91  5032.6 1907.36  5065.6 1919.22
#Mann=3,-1,0
  4814.6     0.1       0  4996.3    0.05       0  5000.3     0.1       0
Bank Sta=4996.3,5000.3
Exp/Cntr=0.3,0.1

Type RM Length L Ch R = 1,15850,470,470,470
BEGIN DESCRIPTION:
Little Lamb Creek 34.0
END DESCRIPTION:
XS GIS Cut Line= 3
      1903424.99     13885125.00      1903575.00     13885075.00
      1903674.98     13885025.01
#Sta/Elev= 30
  4846.2 1928.93  4852.2 1926.55  4865.6 1922.98  4871.9 1920.39  4875.1 1919.95
  4881.4 1917.08  4900.4 1910.37  4916.2 1903.04  4919.4 1902.00  4942.9 1888.53
  4951.0 1882.93  4963.6 1873.12  4976.3 1865.38  4978.5 1863.54  4982.6 1862.15
  4986.9 1861.73  4987.2 1861.23  4990.7 1861.23  4990.9 1861.73  4999.8 1865.24
  5010.8 1872.46  5018.9 1876.24  5035.0 1886.88  5055.1 1896.18  5064.5 1901.34
  5071.9 1904.03  5077.9 1907.54  5082.8 1908.72  5094.0 1914.07  5116.1 1921.98
#Mann=3,-1,0
  4846.2     0.1       0  4986.9    0.05       0  4990.9     0.1       0
Bank Sta=4986.9,4990.9
Exp/Cntr=0.3,0.1

Type RM Length L Ch R = 1,15380,424,424,424
BEGIN DESCRIPTION:
Little Lamb Creek 33.0
END DESCRIPTION:
XS GIS Cut Line= 3
      1903624.99     13885525.00      1903775.00     13885475.00
      1903874.97     13885375.03
#Sta/Elev= 30
  4841.9 1922.02  4852.9 1918.76  4856.0 1916.94  4878.2 1910.12  4884.5 1906.93
  4888.0 1906.59  4900.3 1901.63  4909.8 1895.56  4913.0 1894.39  4922.5 1889.16
  4928.8 1886.63  4952.1 1874.55  4965.0 1863.85  4974.4 1857.81  4982.5 1853.88
  4986.9 1850.99  4987.1 1850.49  4990.6 1850.49  4990.9 1850.99  4997.1 1851.87
  5010.5 1855.97  5035.3 1866.23  5039.5 1867.51  5060.7 1877.75  5073.8 1883.16
  5081.9 1888.11  5099.6 1896.25  5103.8 1899.20  5129.3 1907.90  5141.4 1913.24
#Mann=3,-1,0
  4841.9     0.1       0  4986.9    0.05       0  4990.9     0.1       0
Bank Sta=4986.9,4990.9
Exp/Cntr=0.3,0.1

Type RM Length L Ch R = 1,14956,459,459,459
BEGIN DESCRIPTION:
Little Lamb Creek 32.0
END DESCRIPTION:
XS GIS Cut Line= 3
      1903875.03     13885924.97      1903975.00     13885825.00
      1904125.01     13885624.98
#Sta/Elev= 30
  4858.9 1918.32  4893.4 1904.59  4911.1 1894.33  4915.3 1891.23  4921.3 1889.14
  4927.3 1885.06  4932.3 1882.93  4940.8 1877.60  4953.5 1867.05  4962.0 1856.87
  4966.2 1852.85  4969.7 1848.01  4974.7 1844.20  4976.9 1843.31  4977.2 1842.81
  4980.9 1843.31  4987.4 1843.53  5006.2 1846.76  5034.1 1849.16  5052.7 1855.07
  5074.8 1857.04  5109.3 1865.45  5121.9 1869.77  5144.3 1880.66  5153.9 1888.17
  5168.9 1897.31  5186.2 1902.34  5199.3 1907.67  5213.9 1912.13  5250.3 1921.33
#Mann=3,-1,0
  4858.9     0.1       0  4976.9    0.05       0  4980.9     0.1       0
Bank Sta=4976.9,4980.9
Exp/Cntr=0.3,0.1

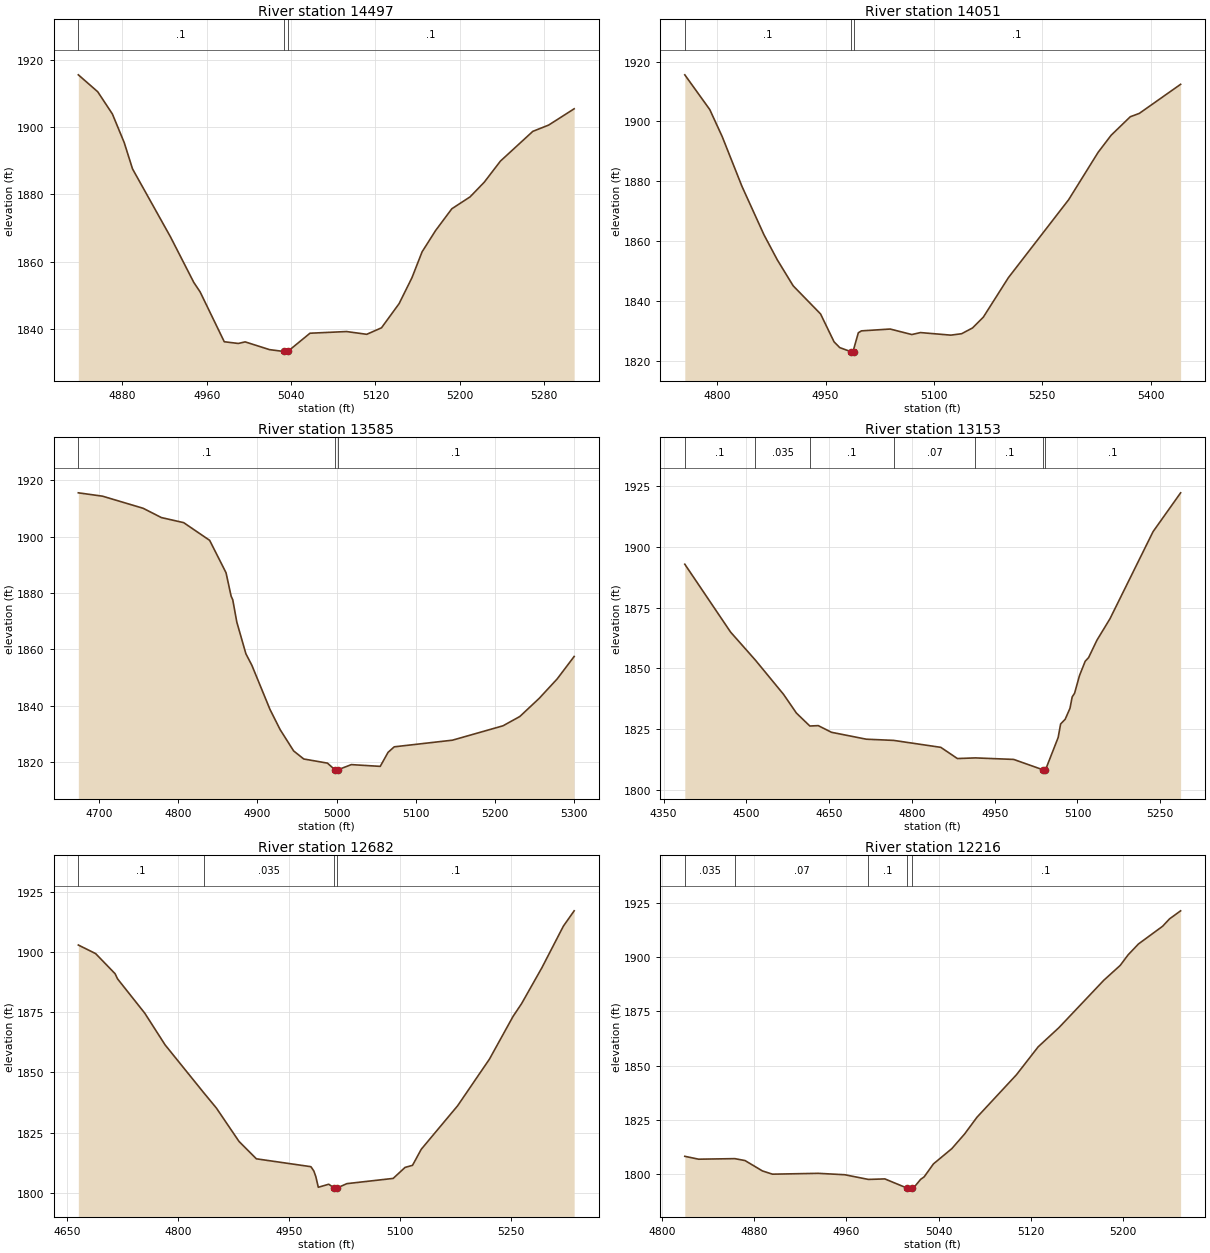
Type RM Length L Ch R = 1,14497,446,446,446
BEGIN DESCRIPTION:
Little Lamb Creek 31.0
END DESCRIPTION:
XS GIS Cut Line= 3
      1904024.98     13886175.00      1904175.00     13886175.00
      1904425.02     13885974.98
#Sta/Elev= 30
  4838.3 1915.53  4856.7 1910.50  4870.6 1903.90  4881.8 1895.41  4889.7 1887.59
  4925.7 1867.39  4947.8 1853.87  4953.8 1851.05  4976.7 1836.25  4990.0 1835.74
  4996.5 1836.21  5019.6 1833.91  5032.9 1833.37  5033.2 1832.87  5036.9 1833.37
  5058.0 1838.78  5092.6 1839.28  5111.8 1838.46  5125.8 1840.39  5142.5 1847.57
  5154.7 1855.28  5164.3 1862.96  5177.1 1869.28  5192.5 1875.75  5209.8 1879.28
  5223.2 1883.62  5238.6 1889.91  5269.3 1898.74  5284.3 1900.60  5308.5 1905.44
#Mann=3,-1,0
  4838.3     0.1       0  5032.9    0.05       0  5036.9     0.1       0
Bank Sta=5032.9,5036.9
Exp/Cntr=0.3,0.1

Type RM Length L Ch R = 1,14051,466,466,466
BEGIN DESCRIPTION:
Little Lamb Creek 30.0
END DESCRIPTION:
XS GIS Cut Line= 3
      1903875.02     13886425.01      1904075.00     13886575.00
      1904511.61     13886578.03
#Sta/Elev= 30
  4755.1 1915.56  4789.7 1903.94  4806.9 1894.91  4834.3 1878.26  4864.7 1862.12
  4883.1 1853.76  4905.2 1845.03  4943.1 1835.64  4961.8 1826.31  4969.7 1824.38
  4984.9 1823.04  4985.1 1822.54  4988.9 1823.04  4989.0 1823.89  4995.4 1829.34
  4999.7 1829.98  5039.5 1830.59  5069.5 1828.75  5081.5 1829.41  5123.5 1828.55
  5138.5 1829.03  5153.5 1830.95  5168.5 1834.57  5203.2 1847.76  5286.6 1873.81
  5327.5 1889.67  5345.5 1895.37  5372.0 1901.55  5384.5 1902.67  5441.7 1912.39
#Mann=3,-1,0
  4755.1     0.1       0  4984.9    0.05       0  4988.9     0.1       0
Bank Sta=4984.9,4988.9
Exp/Cntr=0.3,0.1

Type RM Length L Ch R = 1,13585,432,432,432
BEGIN DESCRIPTION:
Little Lamb Creek 29.0
END DESCRIPTION:
XS GIS Cut Line= 3
      1903575.92     13886621.63      1903775.00     13886875.00
      1904075.04     13886925.01
#Sta/Elev= 30
  4673.8 1915.60  4704.4 1914.41  4755.7 1910.11  4778.7 1906.82  4806.9 1905.01
  4839.7 1898.73  4860.4 1887.23  4866.8 1878.95  4868.9 1877.62  4874.0 1869.72
  4885.5 1858.45  4893.1 1854.33  4916.0 1838.65  4928.7 1831.56  4945.8 1823.96
  4958.6 1821.10  4988.5 1819.63  4997.9 1817.29  4998.2 1816.79  5001.9 1817.29
  5018.7 1819.10  5055.2 1818.48  5065.1 1823.46  5072.9 1825.42  5146.5 1827.78
  5210.3 1832.88  5231.6 1836.19  5256.0 1842.62  5278.7 1849.51  5300.2 1857.50
#Mann=3,-1,0
  4673.8     0.1       0  4997.9    0.05       0  5001.9     0.1       0
Bank Sta=4997.9,5001.9
Exp/Cntr=0.3,0.1

Type RM Length L Ch R = 1,13153,471,471,471
BEGIN DESCRIPTION:
Little Lamb Creek 28.0
END DESCRIPTION:
XS GIS Cut Line= 3
      1903309.43     13887216.68      1903925.00     13887225.00
      1904125.02     13887425.02
#Sta/Elev= 30
  4388.4 1892.75  4471.4 1864.92  4516.4 1853.41  4567.4 1839.38  4590.7 1831.71
  4615.0 1826.42  4630.3 1826.57  4654.2 1823.84  4717.4 1821.01  4766.9 1820.52
  4852.3 1817.67  4882.4 1813.08  4915.1 1813.34  4984.4 1812.72  5038.0 1808.42
  5038.2 1807.92  5042.0 1808.42  5065.0 1821.71  5069.4 1827.23  5077.7 1829.19
  5086.4 1833.68  5090.4 1838.35  5094.7 1839.83  5103.6 1847.07  5114.0 1852.98
  5120.1 1854.45  5135.2 1861.58  5158.8 1870.36  5237.0 1906.12  5286.9 1922.02
#Mann=7,-1,0
  4388.4     0.1       0  4516.4   0.035       0  4615.0     0.1       0
  4766.9    0.07       0  4915.1     0.1       0  5038.0    0.05       0
  5042.0     0.1       0
Bank Sta=5038,5042
Exp/Cntr=0.3,0.1

Type RM Length L Ch R = 1,12682,466,466,466
BEGIN DESCRIPTION:
Little Lamb Creek 27.0
END DESCRIPTION:
XS GIS Cut Line= 3
      1903374.96     13887424.98      1903675.00     13887575.00
      1903975.03     13887725.01
#Sta/Elev= 30
  4665.0 1902.93  4688.5 1899.34  4714.7 1891.02  4718.1 1888.86  4755.0 1874.57
  4782.4 1861.45  4834.9 1841.49  4851.8 1835.21  4882.4 1821.35  4905.9 1814.12
  4979.7 1810.85  4983.7 1809.04  4986.4 1806.69  4989.7 1802.30  5003.8 1803.56
  5011.2 1802.03  5011.5 1801.53  5015.2 1802.03  5028.4 1803.81  5091.0 1805.98
  5107.1 1810.55  5117.2 1811.42  5129.0 1818.08  5178.2 1836.15  5221.2 1855.49
  5253.3 1873.32  5264.8 1878.60  5292.3 1893.52  5321.3 1910.76  5335.9 1917.13
#Mann=4,-1,0
  4665.0     0.1       0  4834.9   0.035       0  5011.2   0.035       0
  5015.2     0.1       0
Bank Sta=5011.2,5015.2
Exp/Cntr=0.3,0.1

Type RM Length L Ch R = 1,12216,460,460,460
BEGIN DESCRIPTION:
Little Lamb Creek 26.0
END DESCRIPTION:
XS GIS Cut Line= 3
      1903575.00     13887925.00      1903725.00     13888025.00
      1903975.02     13888025.00
#Sta/Elev= 30
  4819.7 1808.36  4831.7 1807.04  4863.2 1807.29  4872.0 1806.40  4887.1 1801.63
  4895.8 1800.15  4935.6 1800.53  4958.5 1799.89  4979.1 1797.73  4993.3 1797.97
  5012.5 1793.77  5012.7 1793.27  5016.5 1793.77  5018.4 1793.95  5024.4 1797.78
  5027.4 1798.90  5035.5 1804.88  5051.4 1811.88  5062.5 1818.61  5073.3 1826.36
  5107.5 1845.86  5126.4 1858.74  5144.4 1867.55  5183.4 1889.38  5197.5 1896.14
  5204.4 1901.01  5213.4 1906.03  5234.4 1914.20  5240.4 1917.59  5250.0 1921.28
#Mann=5,-1,0
  4819.7   0.035       0  4863.2    0.07       0  4979.1     0.1       0
  5012.5    0.05       0  5016.5     0.1       0
Bank Sta=5012.5,5016.5
Exp/Cntr=0.3,0.1

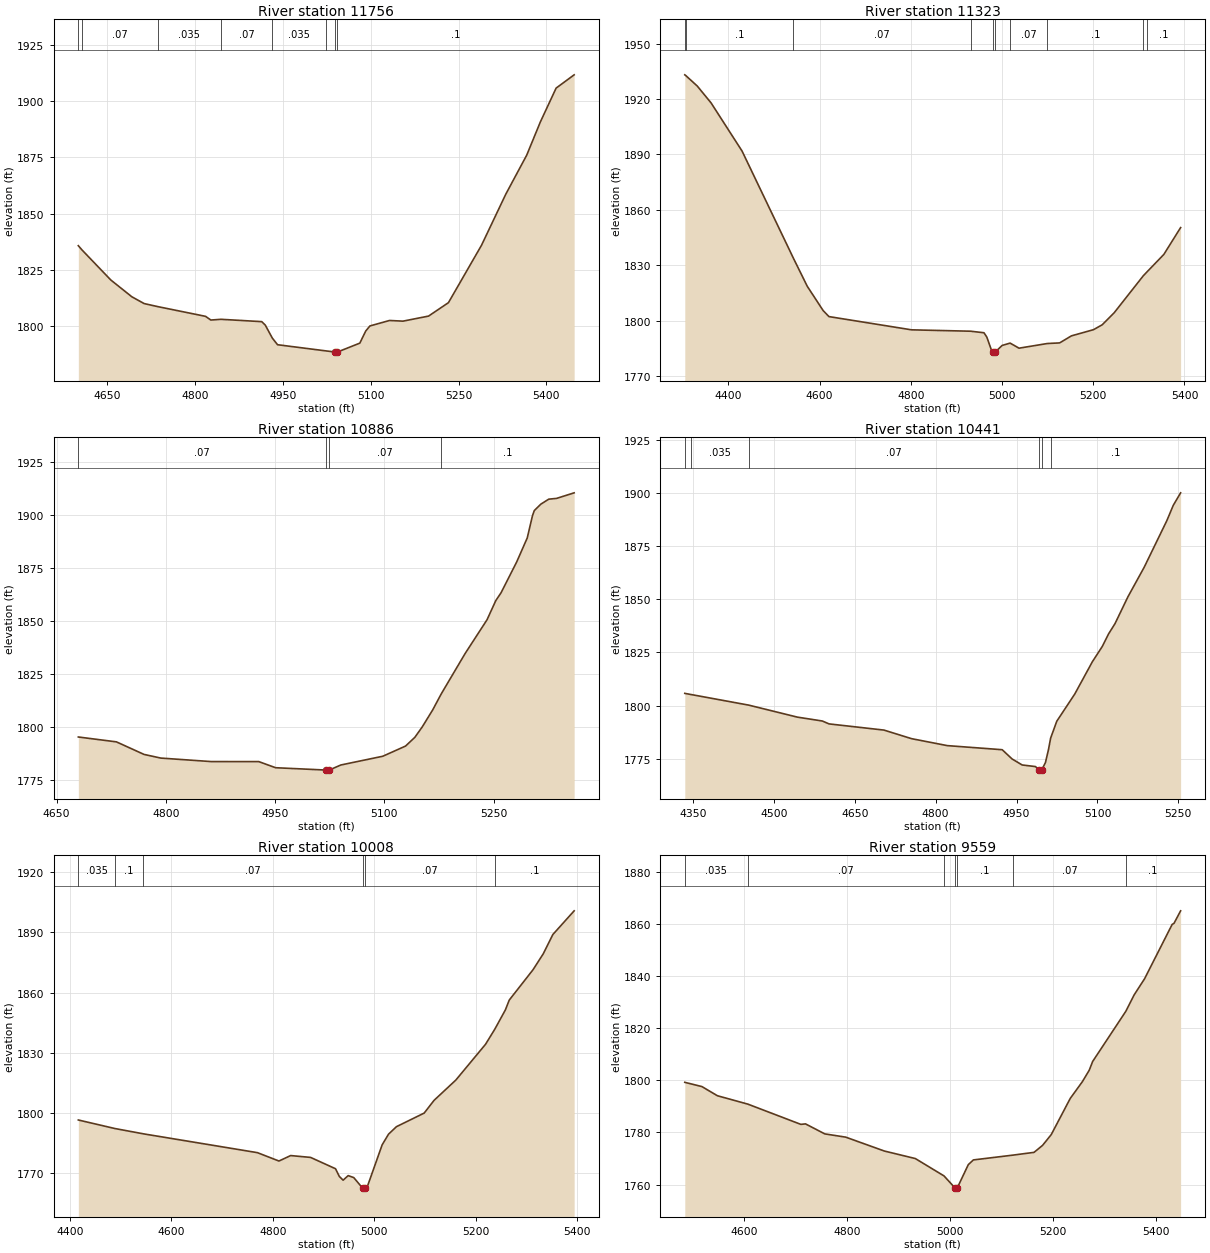
Type RM Length L Ch R = 1,11756,433,433,433
BEGIN DESCRIPTION:
Little Lamb Creek 25.0
END DESCRIPTION:
XS GIS Cut Line= 3
      1903175.00     13888425.00      1903575.00     13888425.00
      1903974.99     13888225.01
#Sta/Elev= 30
  4600.3 1835.73  4606.5 1833.86  4655.7 1820.49  4691.7 1813.00  4712.7 1809.98
  4735.8 1808.63  4817.7 1804.29  4826.7 1802.64  4844.0 1802.97  4913.7 1801.93
  4919.7 1800.40  4931.8 1794.61  4940.7 1791.66  5024.1 1788.89  5038.9 1788.42
  5039.2 1787.92  5043.1 1788.42  5081.3 1792.37  5091.3 1797.72  5098.5 1800.01
  5132.0 1802.45  5155.0 1802.15  5198.7 1804.40  5232.7 1810.38  5289.2 1835.92
  5330.7 1858.66  5366.4 1876.00  5389.8 1890.83  5416.7 1905.86  5447.5 1911.77
#Mann=8,-1,0
  4600.3     0.1       0  4606.5    0.07       0  4735.8   0.035       0
  4844.0    0.07       0  4931.8   0.035       0  5024.1     0.1       0
  5038.9   0.035       0  5043.1     0.1       0
Bank Sta=5038.9,5043.1
Exp/Cntr=0.3,0.1

Type RM Length L Ch R = 1,11323,437,437,437
BEGIN DESCRIPTION:
Little Lamb Creek 24.0
END DESCRIPTION:
XS GIS Cut Line= 3
      1902928.88     13888999.07      1903575.00     13888775.00
      1903975.02     13888725.00
#Sta/Elev= 30
  4304.6 1933.10  4306.8 1932.69  4331.9 1927.03  4362.2 1917.90  4430.1 1891.84
  4542.7 1833.78  4573.0 1818.62  4607.9 1805.42  4620.6 1802.16  4801.6 1794.99
  4931.0 1794.24  4960.4 1793.41  4966.7 1791.08  4976.3 1784.38  4980.5 1782.87
  4980.8 1782.37  4984.8 1782.87  5000.3 1786.53  5017.8 1787.80  5037.3 1785.05
  5099.3 1787.57  5126.4 1787.91  5152.2 1791.72  5200.6 1795.07  5219.7 1797.72
  5245.9 1804.22  5309.6 1824.21  5318.1 1826.42  5354.8 1835.82  5391.6 1850.37
#Mann=10,-1,0
  4304.6    0.07       0  4306.8     0.1       0  4542.7    0.07       0
  4931.0   0.035       0  4980.5   0.035       0  4984.8   0.035       0
  5017.8    0.07       0  5099.3     0.1       0  5309.6    0.07       0
  5318.1     0.1       0
Bank Sta=4980.5,4984.8
Exp/Cntr=0.3,0.1

Type RM Length L Ch R = 1,10886,445,445,445
BEGIN DESCRIPTION:
Little Lamb Creek 23.0
END DESCRIPTION:
XS GIS Cut Line= 3
      1903625.03     13889274.97      1903875.00     13889075.00
      1904175.02     13888874.98
#Sta/Elev= 30
  4679.9 1795.30  4732.2 1793.00  4770.1 1787.07  4793.2 1785.34  4862.3 1783.69
  4927.6 1783.68  4950.7 1780.79  5020.1 1779.68  5020.3 1779.18  5024.4 1779.68
  5040.2 1782.07  5097.9 1786.21  5129.1 1791.01  5141.9 1795.15  5152.0 1800.04
  5166.4 1808.10  5178.1 1815.64  5210.7 1834.61  5241.0 1850.68  5253.0 1859.72
  5260.2 1863.40  5269.1 1869.43  5281.8 1878.05  5296.2 1889.32  5303.4 1899.85
  5305.9 1902.26  5314.9 1905.29  5325.7 1907.63  5336.6 1908.01  5360.6 1910.63
#Mann=4,-1,0
  4679.9    0.07       0  5020.1    0.05       0  5024.4    0.07       0
  5178.1     0.1       0
Bank Sta=5020.1,5024.4
Exp/Cntr=0.3,0.1

Type RM Length L Ch R = 1,10441,433,433,433
BEGIN DESCRIPTION:
Little Lamb Creek 22.0
END DESCRIPTION:
XS GIS Cut Line= 3
      1903474.57     13889582.24      1904125.00     13889425.00
      1904375.04     13889425.00
#Sta/Elev= 30
  4335.0 1805.71  4346.6 1805.17  4453.5 1800.18  4543.7 1794.53  4590.0 1792.70
  4602.4 1791.34  4704.2 1788.43  4755.6 1784.38  4821.5 1781.12  4923.4 1779.19
  4941.9 1774.81  4960.4 1772.01  4985.1 1771.25  4992.1 1769.61  4992.4 1769.11
  4996.6 1769.61  5003.6 1773.15  5009.3 1779.33  5013.2 1784.63  5024.6 1792.59
  5058.0 1805.42  5090.6 1820.60  5109.0 1827.81  5120.6 1833.69  5132.6 1838.56
  5156.6 1851.21  5186.6 1865.05  5228.6 1886.99  5240.6 1894.24  5254.2 1900.11
#Mann=6,-1,0
  4335.0     0.1       0  4346.6   0.035       0  4453.5    0.07       0
  4992.1    0.05       0  4996.6    0.07       0  5013.2     0.1       0
Bank Sta=4992.1,4996.6
Exp/Cntr=0.3,0.1

Type RM Length L Ch R = 1,10008,449,449,449
BEGIN DESCRIPTION:
Little Lamb Creek 21.0
END DESCRIPTION:
XS GIS Cut Line= 3
      1903687.12     13890061.81      1904225.00     13889825.00
      1904474.99     13889525.01
#Sta/Elev= 30
  4416.4 1796.56  4488.3 1792.32  4544.9 1789.66  4769.7 1780.29  4812.2 1776.12
  4835.3 1778.84  4874.6 1777.92  4923.8 1772.28  4931.3 1768.44  4938.8 1766.58
  4948.8 1768.85  4959.8 1767.86  4977.2 1762.62  4977.5 1762.12  4981.7 1762.62
  4986.0 1762.96  5015.8 1784.18  5028.4 1789.50  5044.0 1793.23  5098.7 1800.00
  5118.2 1806.34  5161.2 1816.46  5219.8 1834.29  5237.9 1841.73  5258.8 1851.34
  5266.6 1856.31  5313.5 1871.43  5333.7 1879.38  5352.5 1888.93  5394.6 1900.76
#Mann=6,-1,0
  4416.4   0.035       0  4488.3     0.1       0  4544.9    0.07       0
  4977.2    0.05       0  4981.7    0.07       0  5237.9     0.1       0
Bank Sta=4977.2,4981.7
Exp/Cntr=0.3,0.1

Type RM Length L Ch R = 1,9559,446,446,446
BEGIN DESCRIPTION:
Little Lamb Creek 20.0
END DESCRIPTION:
XS GIS Cut Line= 3
      1903710.32     13890276.90      1904225.00     13890275.00
      1904625.00     13890075.00
#Sta/Elev= 30
  4485.4 1799.25  4518.6 1797.62  4548.6 1794.11  4607.8 1790.88  4710.6 1783.11
  4719.6 1783.30  4757.0 1779.46  4797.6 1778.21  4872.6 1772.88  4932.6 1770.00
  4988.3 1763.33  5009.4 1758.76  5009.8 1758.26  5014.1 1758.76  5035.4 1767.66
  5045.3 1769.47  5122.0 1771.31  5162.9 1772.37  5179.5 1775.06  5196.3 1779.19
  5233.2 1793.08  5256.8 1799.53  5270.1 1803.93  5276.6 1807.24  5341.0 1826.52
  5357.1 1832.80  5377.4 1839.02  5430.9 1859.87  5434.4 1860.26  5447.3 1865.08
#Mann=7,-1,0
  4485.4   0.035       0  4607.8    0.07       0  4988.3     0.1       0
  5009.4    0.05       0  5014.1     0.1       0  5122.0    0.07       0
  5341.0     0.1       0
Bank Sta=5009.4,5014.1
Exp/Cntr=0.3,0.1

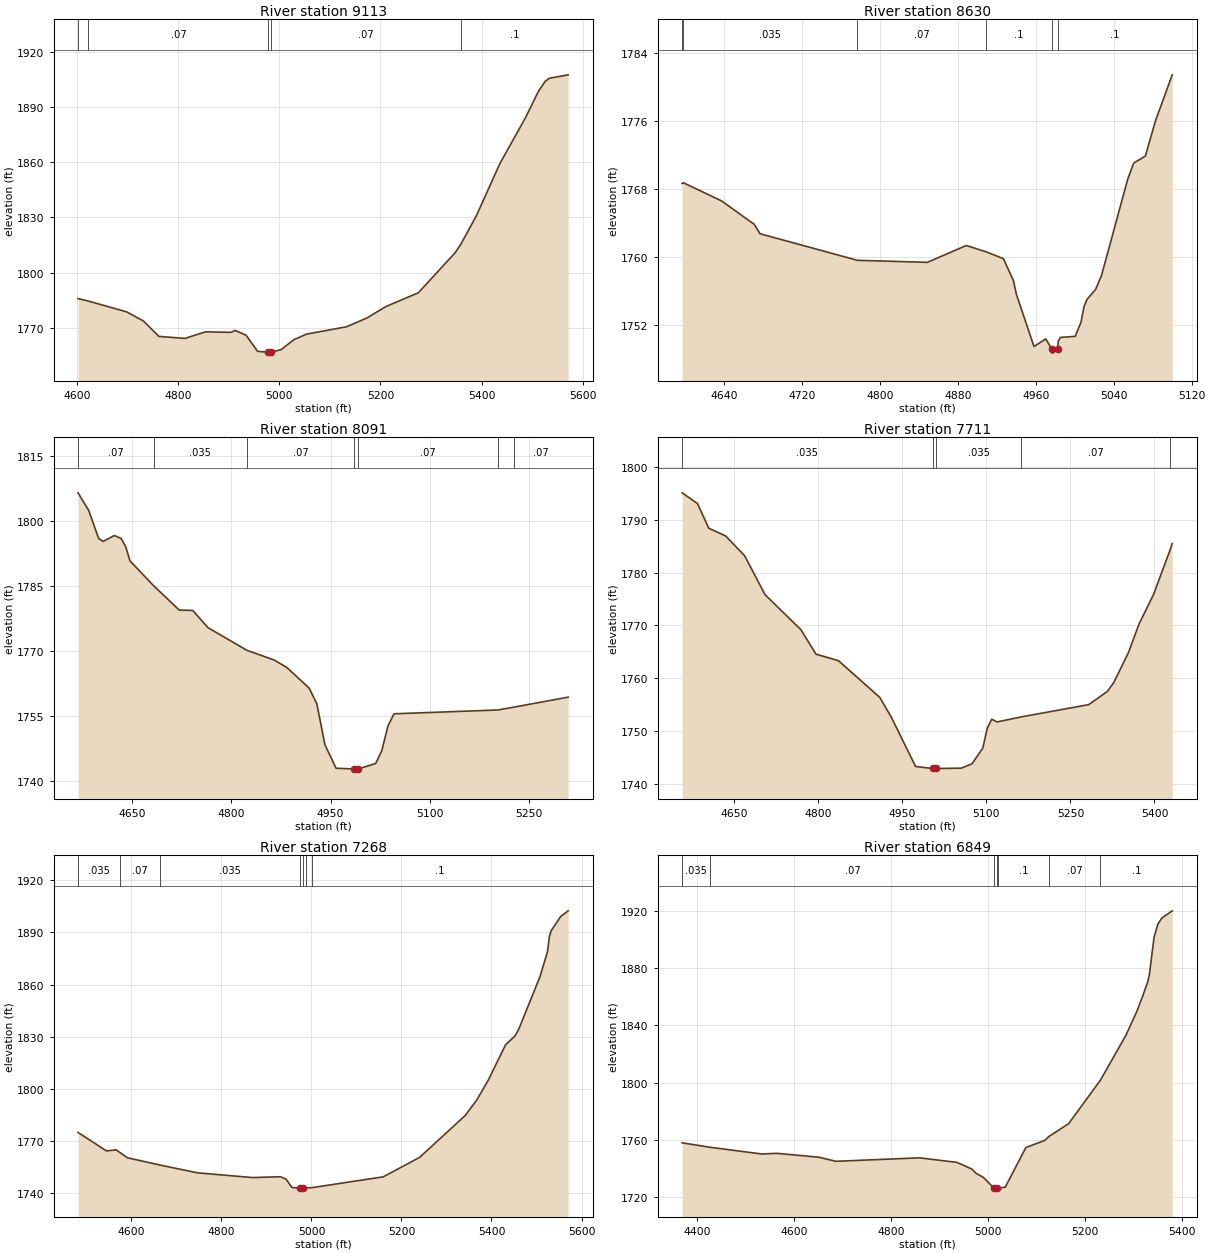
Type RM Length L Ch R = 1,9113,483,483,483
BEGIN DESCRIPTION:
Little Lamb Creek 19.0
END DESCRIPTION:
XS GIS Cut Line= 3
      1903975.04     13890625.00      1904375.00     13890675.00
      1904775.03     13890274.97
#Sta/Elev= 30
  4602.3 1786.03  4622.6 1784.65  4698.5 1778.80  4731.7 1773.83  4762.0 1765.50
  4813.4 1764.41  4854.7 1767.99  4904.1 1767.67  4913.1 1768.69  4934.3 1766.18
  4957.2 1757.38  4978.6 1756.92  4978.9 1756.42  4983.3 1756.92  5003.8 1758.31
  5029.0 1763.74  5054.1 1766.73  5132.8 1770.70  5172.9 1775.42  5211.1 1781.71
  5275.0 1789.16  5347.2 1810.73  5358.5 1815.24  5389.6 1830.87  5436.1 1859.19
  5486.9 1884.18  5512.3 1898.40  5525.4 1903.75  5533.8 1905.48  5571.1 1907.36
#Mann=5,-1,0
  4602.3     0.1       0  4622.6    0.07       0  4978.6    0.05       0
  4983.3    0.07       0  5358.5     0.1       0
Bank Sta=4978.6,4983.3
Exp/Cntr=0.3,0.1

Type RM Length L Ch R = 1,8630,539,539,539
BEGIN DESCRIPTION:
Little Lamb Creek 18.0
END DESCRIPTION:
XS GIS Cut Line= 3
      1904075.04     13891175.00      1904475.00     13891125.00
      1904575.03     13891125.00
#Sta/Elev= 30
  4596.9 1768.65  4598.1 1768.74  4637.6 1766.59  4670.9 1763.85  4676.9 1762.74
  4776.8 1759.62  4848.7 1759.38  4888.6 1761.36  4909.2 1760.61  4926.7 1759.81
  4937.0 1757.24  4940.0 1755.63  4958.1 1749.49  4970.2 1750.38  4976.2 1749.21
  4976.7 1748.71  4982.3 1749.21  4983.1 1750.14  4985.3 1750.56  5000.4 1750.68
  5006.4 1752.36  5009.4 1754.16  5012.4 1755.01  5021.4 1756.21  5027.4 1757.84
  5054.4 1769.18  5060.4 1771.04  5072.4 1771.87  5082.8 1776.01  5100.0 1781.42
#Mann=6,-1,0
  4596.9    0.07       0  4598.1   0.035       0  4776.8    0.07       0
  4909.2     0.1       0  4976.2    0.05       0  4982.3     0.1       0
Bank Sta=4976.2,4982.3
Exp/Cntr=0.3,0.1

Type RM Length L Ch R = 1,8091,380,380,380
BEGIN DESCRIPTION:
Little Lamb Creek 17.0
END DESCRIPTION:
XS GIS Cut Line= 3
      1903841.80     13891744.25      1904231.12     13891541.61
      1904524.97     13891475.01
#Sta/Elev= 30
  4568.6 1806.42  4584.6 1802.40  4599.8 1795.89  4606.6 1795.24  4623.5 1796.60
  4633.6 1795.92  4640.4 1794.09  4647.1 1790.76  4682.6 1785.06  4721.5 1779.43
  4741.8 1779.36  4764.8 1775.40  4823.7 1770.18  4864.9 1767.94  4883.9 1766.24
  4917.7 1761.48  4929.4 1757.80  4941.4 1748.47  4958.3 1743.04  4985.7 1742.88
  4986.2 1742.38  4991.3 1742.38  4991.8 1742.88  5018.1 1744.13  5027.3 1747.08
  5036.6 1752.73  5045.8 1755.57  5202.7 1756.45  5226.7 1757.10  5308.8 1759.40
#Mann=7,-1,0
  4568.6    0.07       0  4682.6   0.035       0  4823.7    0.07       0
  4985.7    0.05       0  4991.8    0.07       0  5202.7   0.035       0
  5226.7    0.07       0
Bank Sta=4985.7,4991.8
Exp/Cntr=0.3,0.1

Type RM Length L Ch R = 1,7711,443,443,443
BEGIN DESCRIPTION:
Little Lamb Creek 16.0
END DESCRIPTION:
XS GIS Cut Line= 3
      1904024.98     13892025.01      1904425.00     13891825.00
      1904824.97     13891675.01
#Sta/Elev= 30
  4557.3 1795.14  4584.7 1793.11  4604.8 1788.44  4635.0 1786.96  4668.7 1783.24
  4705.4 1775.82  4769.2 1769.21  4796.1 1764.57  4836.2 1763.33  4910.0 1756.37
  4930.2 1752.69  4973.8 1743.28  5004.1 1742.90  5004.6 1742.40  5010.3 1742.90
  5055.2 1742.96  5074.5 1743.79  5093.7 1746.76  5101.7 1750.52  5109.7 1752.24
  5119.3 1751.72  5162.5 1752.68  5282.7 1755.00  5316.1 1757.51  5327.6 1759.22
  5353.9 1764.94  5372.4 1770.26  5398.1 1775.81  5428.4 1784.45  5431.7 1785.52
#Mann=5,-1,0
  4557.3   0.035       0  5004.1   0.035       0  5010.3   0.035       0
  5162.5    0.07       0  5428.4     0.1       0
Bank Sta=5004.1,5010.3
Exp/Cntr=0.3,0.1

Type RM Length L Ch R = 1,7268,419,419,419
BEGIN DESCRIPTION:
Little Lamb Creek 15.0
END DESCRIPTION:
XS GIS Cut Line= 3
      1904171.78     13892318.03      1904675.00     13892175.00
      1905074.98     13891775.02
#Sta/Elev= 30
  4481.5 1775.04  4544.6 1764.44  4566.4 1765.01  4573.7 1763.61  4591.4 1760.47
  4664.0 1756.28  4747.3 1751.81  4868.9 1749.11  4931.3 1749.58  4943.8 1748.18
  4956.3 1743.46  4975.0 1742.96  4975.5 1742.46  4981.2 1742.96  4987.3 1743.17
  5001.1 1743.31  5159.6 1749.52  5240.4 1760.74  5341.9 1784.84  5367.4 1793.73
  5393.1 1805.23  5431.3 1825.44  5452.2 1830.44  5460.7 1834.44  5507.7 1864.54
  5524.3 1878.83  5528.6 1887.68  5532.8 1891.09  5554.0 1899.25  5570.3 1902.41
#Mann=7,-1,0
  4481.5   0.035       0  4573.7    0.07       0  4664.0   0.035       0
  4975.0    0.05       0  4981.2   0.035       0  4987.3    0.07       0
  5001.1     0.1       0
Bank Sta=4975,4981.2
Exp/Cntr=0.3,0.1

Type RM Length L Ch R = 1,6849,470,470,470
BEGIN DESCRIPTION:
Little Lamb Creek 14.0
END DESCRIPTION:
XS GIS Cut Line= 3
      1904296.03     13892436.53      1904925.00     13892475.00
      1905274.97     13892624.99
#Sta/Elev= 30
  4369.3 1757.97  4427.7 1754.83  4534.0 1750.15  4564.1 1750.64  4651.3 1747.92
  4686.7 1745.06  4858.7 1747.48  4936.0 1744.31  4966.9 1739.65  4975.9 1736.61
  4990.9 1733.77  5013.1 1726.11  5013.6 1725.61  5019.4 1726.11  5020.4 1726.29
  5035.9 1727.00  5078.3 1754.65  5117.5 1759.70  5126.2 1762.50  5166.4 1771.32
  5232.0 1801.70  5284.6 1833.07  5307.0 1849.63  5319.8 1860.98  5329.8 1870.71
  5332.9 1875.14  5342.7 1901.63  5350.4 1910.71  5359.0 1915.18  5380.2 1920.13
#Mann=7,-1,0
  4369.3   0.035       0  4427.7    0.07       0  5013.1    0.05       0
  5019.4    0.07       0  5020.4     0.1       0  5126.2    0.07       0
  5232.0     0.1       0
Bank Sta=5013.1,5019.4
Exp/Cntr=0.3,0.1

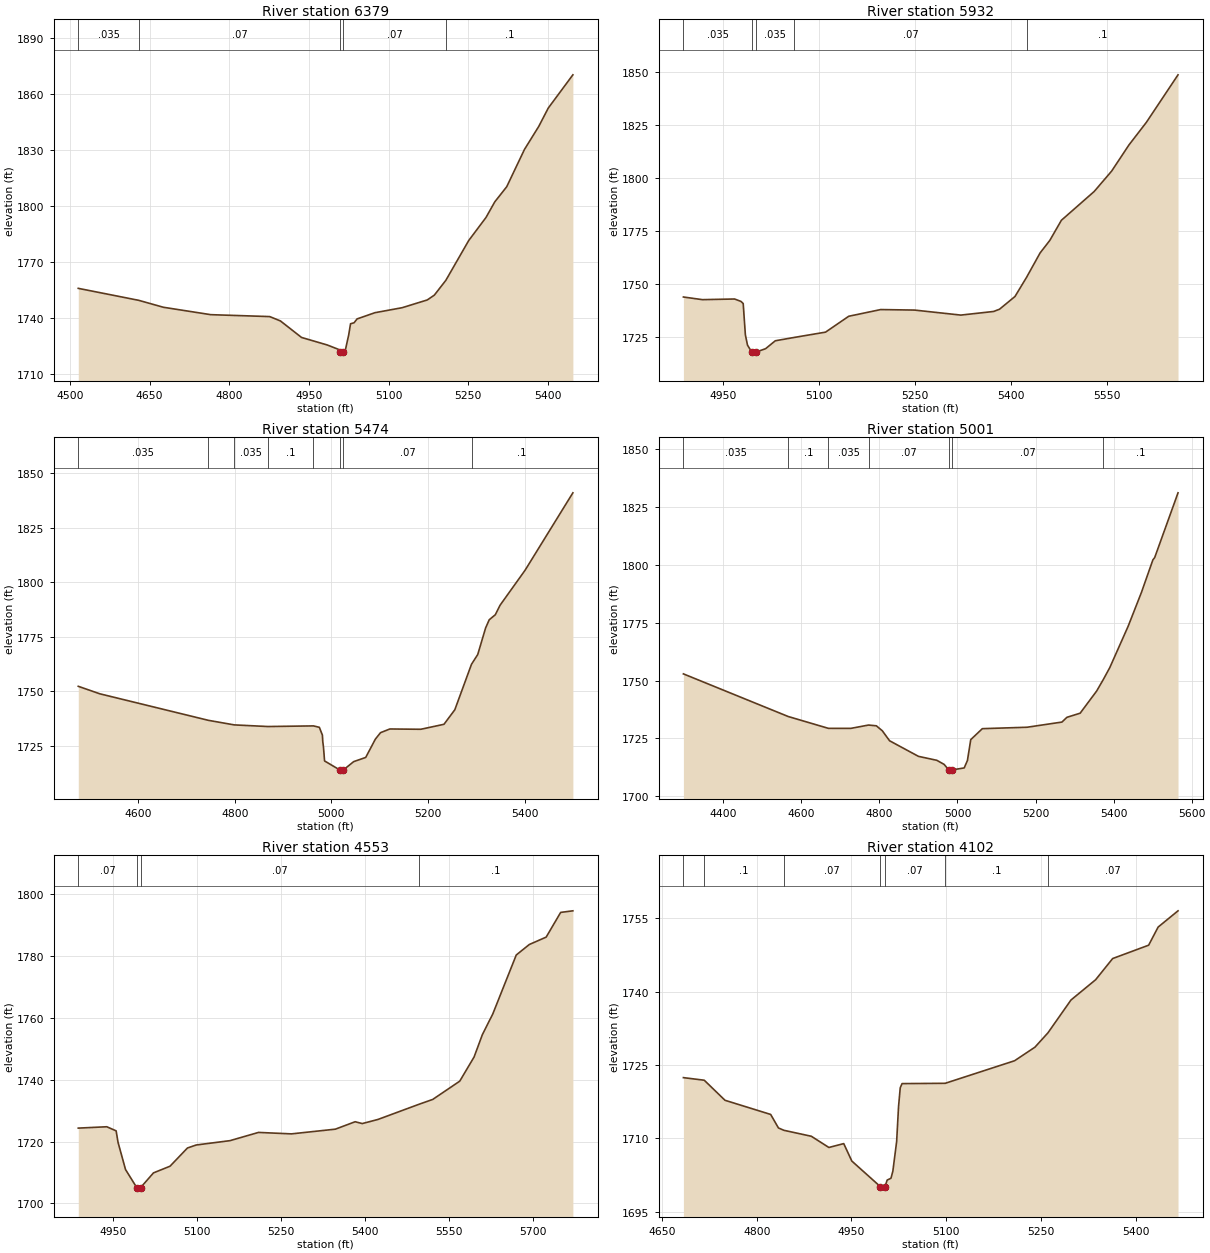
Type RM Length L Ch R = 1,6379,447,447,447
BEGIN DESCRIPTION:
Little Lamb Creek 13.0
END DESCRIPTION:
XS GIS Cut Line= 3
      1904246.65     13892599.24      1904675.00     13892825.00
      1905074.99     13893024.99
#Sta/Elev= 30
  4515.8 1755.95  4629.6 1749.54  4676.1 1745.82  4765.2 1741.86  4876.3 1740.83
  4896.5 1738.50  4936.2 1729.66  4984.7 1725.62  5007.3 1723.10  5008.7 1721.76
  5009.2 1721.26  5015.1 1721.76  5018.6 1722.69  5025.1 1731.09  5028.5 1736.98
  5035.2 1737.53  5040.8 1739.58  5074.4 1742.91  5125.7 1745.59  5172.9 1749.73
  5186.3 1752.32  5208.0 1760.26  5251.0 1781.54  5283.4 1793.83  5300.2 1802.30
  5322.6 1810.37  5356.1 1830.38  5383.0 1842.71  5400.8 1852.49  5447.2 1870.31
#Mann=5,-1,0
  4515.8   0.035       0  4629.6    0.07       0  5008.7    0.05       0
  5015.1    0.07       0  5208.0     0.1       0
Bank Sta=5008.7,5015.1
Exp/Cntr=0.3,0.1

Type RM Length L Ch R = 1,5932,458,458,458
BEGIN DESCRIPTION:
Little Lamb Creek 12.0
END DESCRIPTION:
XS GIS Cut Line= 3
      1904275.02     13893174.99      1904375.00     13893125.00
      1905031.55     13893057.37
#Sta/Elev= 30
  4888.7 1744.01  4918.3 1742.76  4968.6 1743.07  4978.6 1741.92  4982.0 1740.94
  4985.4 1726.23  4988.7 1721.37  4995.4 1718.11  4995.9 1717.61  5002.2 1718.11
  5017.0 1719.71  5032.1 1723.42  5061.3 1724.97  5110.5 1727.48  5146.7 1734.95
  5196.6 1738.10  5249.3 1737.86  5321.6 1735.50  5372.9 1737.21  5382.0 1738.27
  5406.1 1744.25  5424.3 1753.33  5445.3 1764.74  5460.4 1770.60  5478.5 1780.09
  5529.7 1793.64  5556.9 1803.22  5584.0 1815.55  5611.2 1826.19  5660.5 1848.51
#Mann=5,-1,0
  4888.7   0.035       0  4995.4   0.035       0  5002.2   0.035       0
  5061.3    0.07       0  5424.3     0.1       0
Bank Sta=4995.4,5002.2
Exp/Cntr=0.3,0.1

Type RM Length L Ch R = 1,5474,473,473,473
BEGIN DESCRIPTION:
Little Lamb Creek 11.0
END DESCRIPTION:
XS GIS Cut Line= 3
      1904196.03     13893725.91      1904625.00     13893425.00
      1905025.01     13893124.99
#Sta/Elev= 30
  4476.0 1752.23  4520.5 1748.80  4745.4 1736.63  4798.9 1734.54  4868.6 1733.79
  4962.8 1734.08  4975.1 1733.43  4981.4 1729.88  4982.2 1726.90  4983.6 1724.50
  4985.9 1718.02  5017.7 1713.85  5018.2 1713.35  5024.6 1713.85  5046.1 1717.69
  5071.1 1719.63  5091.1 1728.02  5101.8 1730.98  5121.1 1732.67  5185.1 1732.53
  5233.1 1734.81  5255.6 1741.49  5290.1 1762.33  5303.0 1766.79  5319.3 1778.96
  5326.8 1782.72  5339.4 1785.03  5349.3 1789.41  5401.1 1805.45  5500.0 1840.91
#Mann=8,-1,0
  4476.0   0.035       0  4745.4     0.1       0  4798.9   0.035       0
  4868.6     0.1       0  4962.8    0.07       0  5017.7    0.05       0
  5024.6    0.07       0  5290.1     0.1       0
Bank Sta=5017.7,5024.6
Exp/Cntr=0.3,0.1

Type RM Length L Ch R = 1,5001,448,448,448
BEGIN DESCRIPTION:
Little Lamb Creek 10.0
END DESCRIPTION:
XS GIS Cut Line= 3
      1904247.15     13893906.48      1904925.00     13893725.00
      1905324.99     13893325.01
#Sta/Elev= 30
  4297.7 1752.89  4566.2 1734.47  4669.3 1729.35  4726.6 1729.34  4772.2 1730.78
  4792.1 1730.45  4807.4 1728.30  4826.0 1723.99  4899.9 1717.26  4947.1 1715.54
  4965.7 1713.79  4977.8 1711.37  4978.3 1710.87  4984.7 1711.37  5017.2 1712.25
  5025.5 1715.47  5034.0 1724.48  5063.7 1729.22  5178.3 1729.83  5267.7 1732.07
  5280.4 1734.12  5314.3 1735.90  5356.5 1745.45  5374.0 1750.55  5390.4 1755.65
  5437.4 1773.50  5471.3 1788.07  5500.7 1802.14  5505.3 1803.13  5565.1 1831.12
#Mann=7,-1,0
  4297.7   0.035       0  4566.2     0.1       0  4669.3   0.035       0
  4772.2    0.07       0  4977.8    0.05       0  4984.7    0.07       0
  5374.0     0.1       0
Bank Sta=4977.8,4984.7
Exp/Cntr=0.3,0.1

Type RM Length L Ch R = 1,4553,451,451,451
BEGIN DESCRIPTION:
Little Lamb Creek 9.0
END DESCRIPTION:
XS GIS Cut Line= 3
      1904924.97     13894175.02      1905025.00     13894125.00
      1905521.54     13893534.84
#Sta/Elev= 30
  4888.1 1724.35  4939.0 1724.79  4955.7 1723.47  4959.1 1719.76  4972.5 1710.96
  4992.5 1705.14  4993.0 1704.64  4999.4 1705.14  5022.4 1709.89  5051.9 1712.04
  5083.0 1717.92  5098.7 1718.90  5159.0 1720.30  5209.9 1722.96  5268.7 1722.49
  5347.1 1724.01  5382.4 1726.41  5395.2 1725.82  5423.2 1727.15  5496.1 1732.03
  5521.0 1733.62  5569.2 1739.52  5594.8 1747.33  5609.6 1754.55  5628.2 1761.24
  5670.1 1780.28  5693.4 1783.67  5723.5 1786.06  5749.4 1794.04  5771.2 1794.55
#Mann=4,-1,0
  4888.1    0.07       0  4992.5    0.05       0  4999.4    0.07       0
  5496.1     0.1       0
Bank Sta=4992.5,4999.4
Exp/Cntr=0.3,0.1

Type RM Length L Ch R = 1,4102,448,448,448
BEGIN DESCRIPTION:
Little Lamb Creek 8.0
END DESCRIPTION:
XS GIS Cut Line= 3
      1904924.98     13894324.98      1905175.00     13894525.00
      1905637.94     13894537.51
#Sta/Elev= 30
  4683.8 1722.41  4716.8 1721.88  4749.7 1717.78  4822.0 1714.89  4834.3 1712.13
  4842.9 1711.65  4886.4 1710.43  4914.2 1708.14  4937.7 1708.93  4950.5 1705.37
  4995.8 1700.13  4996.3 1699.63  5003.1 1700.13  5006.5 1701.48  5012.5 1701.85
  5015.5 1703.30  5021.5 1709.35  5024.5 1716.47  5027.2 1720.34  5030.1 1721.19
  5098.4 1721.25  5208.3 1725.86  5240.5 1728.63  5261.1 1731.56  5297.6 1738.27
  5336.6 1742.41  5363.6 1746.74  5420.6 1749.47  5435.6 1753.17  5467.1 1756.49
#Mann=7,-1,0
  4683.8    0.07       0  4716.8     0.1       0  4842.9    0.07       0
  4995.8    0.05       0  5003.1    0.07       0  5098.4     0.1       0
  5261.1    0.07       0
Bank Sta=4995.8,5003.1
Exp/Cntr=0.3,0.1