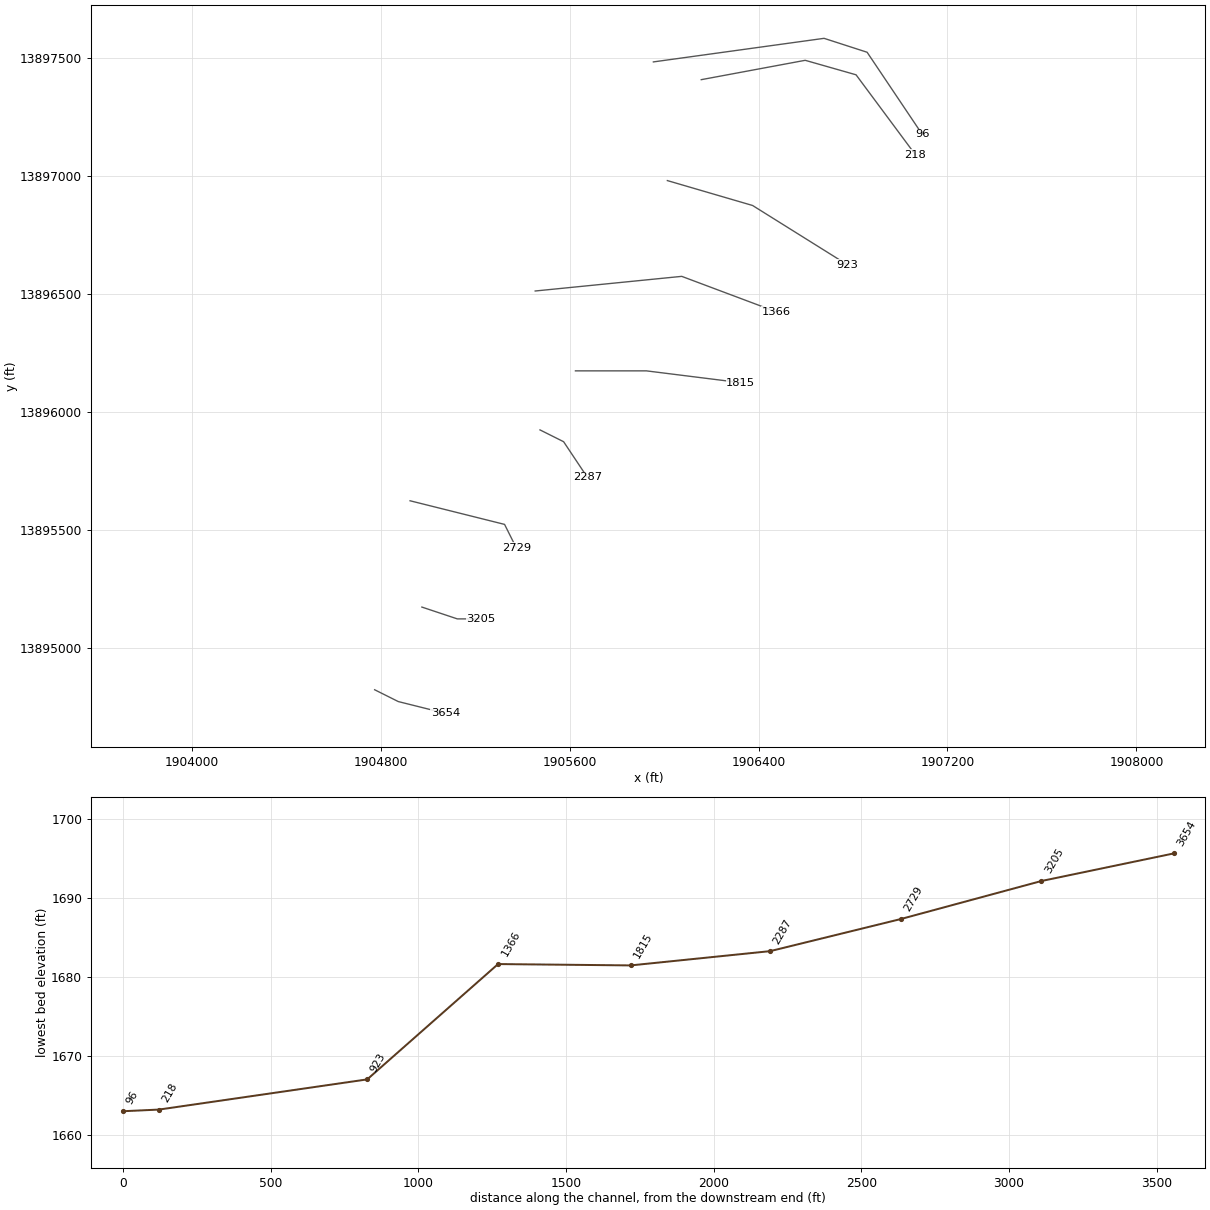
HEC-RAS study Little Lamb Creek.prj: Little Lamb Creek Base Level Engineering

--- Little Lamb Creek.g01 (geometry) --- (continued)

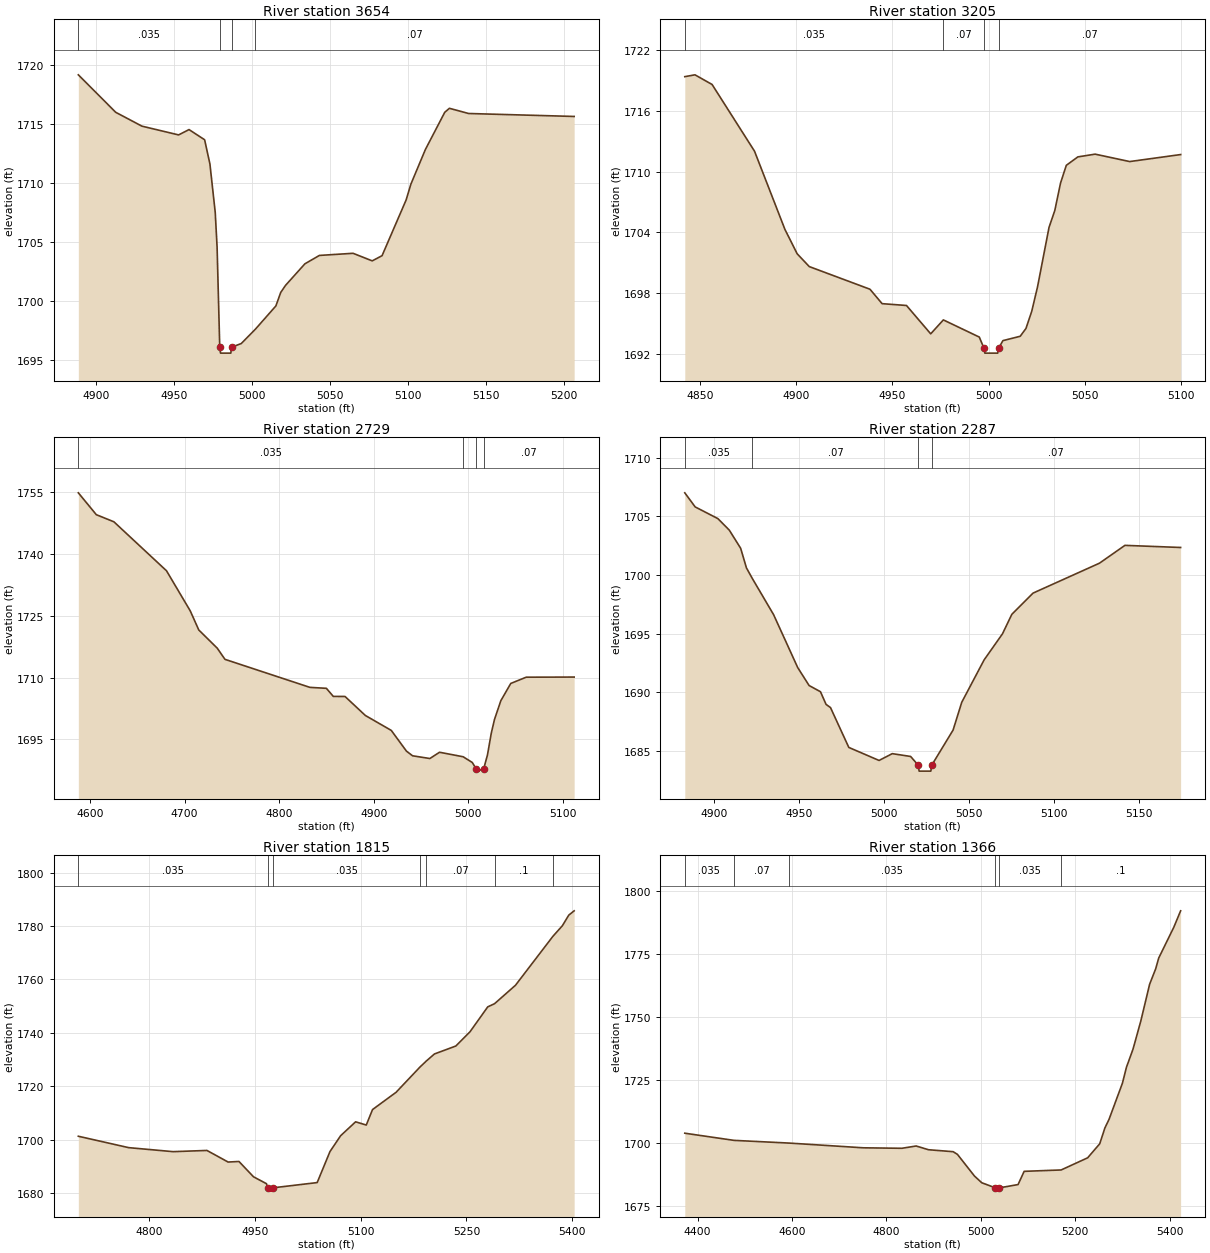
Type RM Length L Ch R = 1,3654,449,449,449
BEGIN DESCRIPTION:
Little Lamb Creek 7.0
END DESCRIPTION:
XS GIS Cut Line= 3
      1904774.98     13894825.01      1904875.00     13894775.00
      1905075.02     13894724.99
#Sta/Elev= 30
  4888.8 1719.14  4912.8 1715.97  4929.6 1714.80  4953.1 1714.06  4959.8 1714.51
  4969.8 1713.65  4973.2 1711.60  4976.6 1707.51  4977.8 1704.56  4979.5 1696.11
  4980.0 1695.61  4986.6 1695.61  4987.1 1696.11  4993.3 1696.42  5002.4 1697.64
  5015.5 1699.60  5018.6 1700.74  5021.7 1701.34  5034.1 1703.16  5043.4 1703.87
  5065.0 1704.05  5077.3 1703.41  5083.6 1703.85  5099.0 1708.55  5102.1 1709.90
  5111.4 1712.83  5123.8 1715.97  5126.8 1716.31  5139.1 1715.87  5206.8 1715.62
#Mann=4,-1,0
  4888.8   0.035       0  4979.5   0.035       0  4987.1   0.035       0
  5002.4    0.07       0
Bank Sta=4979.5,4987.1
Exp/Cntr=0.3,0.1

Type RM Length L Ch R = 1,3205,476,476,476
BEGIN DESCRIPTION:
Little Lamb Creek 6.0
END DESCRIPTION:
XS GIS Cut Line= 3
      1904975.01     13895175.00      1905125.00     13895125.00
      1905225.00     13895125.00
#Sta/Elev= 30
  4841.9 1719.34  4847.2 1719.52  4856.1 1718.57  4878.2 1712.00  4894.0 1704.31
  4900.4 1701.90  4906.7 1700.64  4938.3 1698.41  4944.6 1696.99  4957.3 1696.81
  4969.9 1694.02  4976.5 1695.39  4995.2 1693.70  4997.6 1692.62  4998.1 1692.12
  5004.8 1692.12  5005.3 1692.62  5007.5 1693.35  5016.5 1693.78  5019.5 1694.55
  5022.5 1696.24  5025.5 1698.63  5031.5 1704.50  5034.5 1706.16  5037.5 1708.87
  5040.5 1710.61  5046.5 1711.44  5055.5 1711.71  5073.5 1710.98  5100.0 1711.67
#Mann=4,-1,0
  4841.9   0.035       0  4976.5    0.07       0  4997.6    0.05       0
  5005.3    0.07       0
Bank Sta=4997.6,5005.3
Exp/Cntr=0.3,0.1

Type RM Length L Ch R = 1,2729,442,442,442
BEGIN DESCRIPTION:
Little Lamb Creek 5.0
END DESCRIPTION:
XS GIS Cut Line= 3
      1904925.00     13895625.00      1905325.00     13895525.00
      1905374.99     13895425.01
#Sta/Elev= 30
  4587.7 1754.84  4606.7 1749.54  4625.3 1747.81  4680.9 1735.93  4706.0 1726.20
  4715.0 1721.57  4734.5 1717.16  4742.7 1714.44  4832.5 1707.64  4849.9 1707.41
  4857.2 1705.45  4869.6 1705.43  4891.1 1700.82  4918.5 1697.20  4934.5 1692.18
  4941.0 1691.04  4959.3 1690.38  4969.5 1691.90  4994.4 1690.81  5004.1 1689.42
  5008.4 1687.82  5008.9 1687.32  5016.1 1687.82  5020.2 1691.28  5024.2 1696.53
  5027.6 1699.86  5034.3 1704.41  5044.8 1708.59  5061.1 1710.11  5111.8 1710.14
#Mann=4,-1,0
  4587.7   0.035       0  4994.4    0.07       0  5008.4    0.05       0
  5016.1    0.07       0
Bank Sta=5008.4,5016.1
Exp/Cntr=0.3,0.1

Type RM Length L Ch R = 1,2287,472,472,472
BEGIN DESCRIPTION:
Little Lamb Creek 4.0
END DESCRIPTION:
XS GIS Cut Line= 3
      1905475.03     13895924.99      1905575.00     13895875.00
      1905674.97     13895725.04
#Sta/Elev= 30
  4882.8 1707.00  4888.9 1705.80  4902.3 1704.80  4909.0 1703.82  4915.7 1702.27
  4919.1 1700.60  4922.6 1699.69  4935.1 1696.61  4949.3 1692.10  4956.0 1690.57
  4962.7 1690.04  4966.0 1688.96  4968.6 1688.69  4979.4 1685.29  4997.2 1684.18
  5005.0 1684.76  5015.8 1684.52  5020.3 1683.77  5020.8 1683.27  5027.7 1683.27
  5028.2 1683.77  5040.8 1686.77  5045.9 1689.14  5059.1 1692.76  5069.9 1694.98
  5075.4 1696.64  5087.9 1698.45  5127.0 1701.00  5142.0 1702.52  5174.8 1702.34
#Mann=4,-1,0
  4882.8   0.035       0  4922.6    0.07       0  5020.3    0.05       0
  5028.2    0.07       0
Bank Sta=5020.3,5028.2
Exp/Cntr=0.3,0.1

Type RM Length L Ch R = 1,1815,449,449,449
BEGIN DESCRIPTION:
Little Lamb Creek 3.0
END DESCRIPTION:
XS GIS Cut Line= 3
      1905625.03     13896175.00      1905925.00     13896175.00
      1906325.02     13896125.00
#Sta/Elev= 30
  4699.7 1701.27  4771.1 1697.00  4834.1 1695.50  4882.1 1695.95  4912.1 1691.61
  4927.5 1691.82  4948.1 1686.09  4966.5 1683.50  4968.1 1681.97  4968.6 1681.47
  4976.1 1681.97  5038.4 1683.92  5056.6 1695.56  5071.7 1701.48  5092.9 1706.67
  5108.0 1705.46  5116.9 1711.26  5150.3 1717.73  5184.2 1727.19  5193.3 1729.47
  5204.7 1732.08  5235.0 1735.05  5255.1 1740.38  5280.3 1749.72  5289.9 1750.89
  5319.6 1757.80  5372.6 1776.10  5386.1 1780.09  5395.2 1784.07  5402.8 1785.67
#Mann=7,-1,0
  4699.7   0.035       0  4968.1   0.035       0  4976.1   0.035       0
  5184.2     0.1       0  5193.3    0.07       0  5289.9     0.1       0
  5372.6    0.07       0
Bank Sta=4968.1,4976.1
Exp/Cntr=0.3,0.1

Type RM Length L Ch R = 1,1366,443,443,443
BEGIN DESCRIPTION:
Little Lamb Creek 2.0
END DESCRIPTION:
XS GIS Cut Line= 3
      1905454.74     13896513.05      1906075.00     13896575.00
      1906474.95     13896425.02
#Sta/Elev= 30
  4372.9 1703.81  4477.1 1700.97  4593.5 1699.90  4751.2 1698.02  4832.9 1697.83
  4863.1 1698.74  4889.2 1697.26  4941.4 1696.48  4950.5 1695.43  4986.7 1686.81
  5002.1 1684.17  5031.1 1682.14  5031.6 1681.64  5039.2 1682.14  5079.0 1683.45
  5091.9 1688.69  5170.3 1689.24  5226.4 1694.05  5252.0 1699.61  5263.0 1705.92
  5271.6 1709.24  5300.1 1723.63  5308.6 1729.94  5322.5 1737.11  5338.9 1748.17
  5357.7 1762.84  5370.6 1769.01  5377.0 1773.26  5409.0 1785.47  5423.4 1791.97
#Mann=6,-1,0
  4372.9   0.035       0  4477.1    0.07       0  4593.5   0.035       0
  5031.1   0.035       0  5039.2   0.035       0  5170.3     0.1       0
Bank Sta=5031.1,5039.2
Exp/Cntr=0.3,0.1

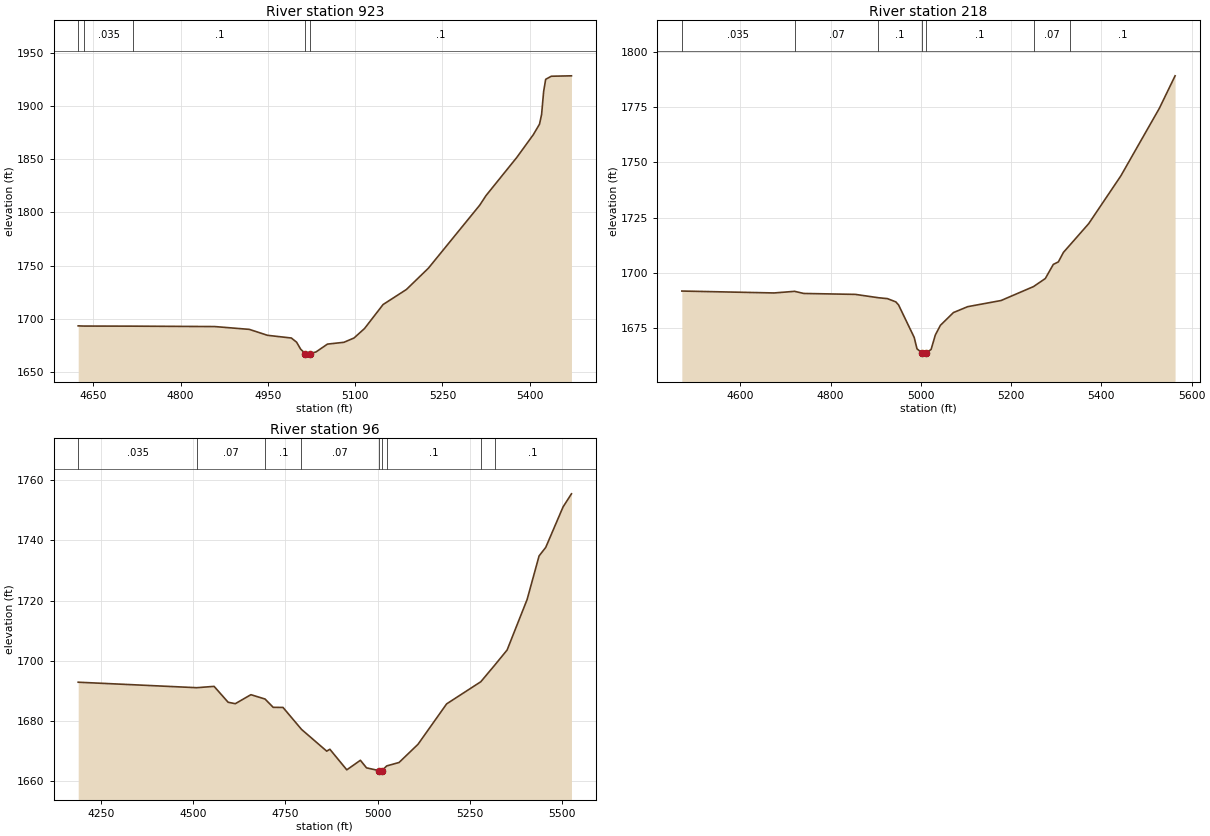
Type RM Length L Ch R = 1,923,705,705,705
BEGIN DESCRIPTION:
Little Lamb Creek 1.0
END DESCRIPTION:
XS GIS Cut Line= 3
      1906014.20     13896980.45      1906375.00     13896875.00
      1906775.01     13896624.99
#Sta/Elev= 30
  4624.1 1693.60  4633.8 1693.42  4719.0 1693.33  4858.8 1692.95  4918.2 1690.30
  4949.4 1684.74  4990.4 1682.20  4999.4 1678.27  5006.4 1671.70  5014.2 1667.58
  5014.7 1667.08  5022.3 1667.58  5032.8 1669.14  5052.4 1676.48  5080.7 1678.18
  5098.1 1682.23  5116.1 1691.10  5148.0 1713.62  5188.1 1727.75  5225.8 1747.68
  5314.2 1806.95  5324.8 1815.81  5377.9 1851.76  5406.2 1873.06  5416.8 1882.90
  5420.4 1892.00  5423.9 1913.52  5427.4 1924.97  5437.1 1927.87  5471.7 1928.25
#Mann=5,-1,0
  4624.1    0.07       0  4633.8   0.035       0  4719.0     0.1       0
  5014.2    0.05       0  5022.3     0.1       0
Bank Sta=5014.2,5022.3
Exp/Cntr=0.3,0.1

Type RM Length L Ch R = 1,218,122,122,122
BEGIN DESCRIPTION:
Little Lamb Creek 0.0
END DESCRIPTION:
XS GIS Cut Line= 4
      1906157.71     13897407.67      1906597.67     13897489.60
      1906812.96     13897428.25      1907064.27     13897089.71
#Sta/Elev= 30
  4470.3 1691.78  4674.7 1690.92  4720.2 1691.65  4740.4 1690.69  4854.8 1690.27
  4905.8 1688.76  4925.9 1688.35  4944.6 1686.87  4950.6 1685.49  4985.2 1670.82
  4991.4 1665.67  5002.7 1663.77  5003.2 1663.27  5011.0 1663.77  5022.6 1665.36
  5032.0 1671.91  5043.3 1676.30  5072.1 1682.05  5103.7 1684.72  5177.7 1687.50
  5249.6 1693.80  5275.7 1697.43  5293.5 1703.83  5304.7 1704.96  5315.9 1709.27
  5329.5 1712.40  5372.0 1722.28  5443.0 1743.80  5528.4 1774.36  5563.3 1789.05
#Mann=7,-1,0
  4470.3   0.035       0  4720.2    0.07       0  4905.8     0.1       0
  5002.7    0.05       0  5011.0     0.1       0  5249.6    0.07       0
  5329.5     0.1       0
Bank Sta=5002.7,5011
Exp/Cntr=0.3,0.1

Type RM Length L Ch R = 1,96,0,0,0
BEGIN DESCRIPTION:
Little Lamb Creek 0.1
END DESCRIPTION:
XS GIS Cut Line= 4
      1905954.98     13897482.83      1906677.44     13897582.62
      1906859.77     13897523.71      1907092.96     13897176.36
#Sta/Elev= 30
  4187.2 1692.90  4508.9 1691.08  4556.2 1691.52  4594.3 1686.25  4613.7 1685.77
  4656.1 1688.76  4694.5 1687.32  4716.7 1684.56  4743.3 1684.53  4793.5 1677.25
  4862.0 1670.02  4870.5 1670.65  4916.5 1663.82  4953.4 1666.99  4970.1 1664.48
  5003.8 1663.56  5004.3 1663.06  5012.1 1663.56  5024.8 1665.12  5058.4 1666.26
  5109.8 1672.29  5187.6 1685.71  5280.4 1693.06  5318.9 1698.67  5351.8 1703.59
  5406.1 1720.35  5438.6 1734.81  5456.7 1737.65  5503.7 1751.07  5526.5 1755.42
#Mann=9,-1,0
  4187.2   0.035       0  4508.9    0.07       0  4694.5     0.1       0
  4793.5    0.07       0  5003.8    0.05       0  5012.1    0.07       0
  5024.8     0.1       0  5280.4    0.07       0  5318.9     0.1       0
Bank Sta=5003.8,5012.1
Exp/Cntr=0.3,0.1

Chan Stop Cuts=-1