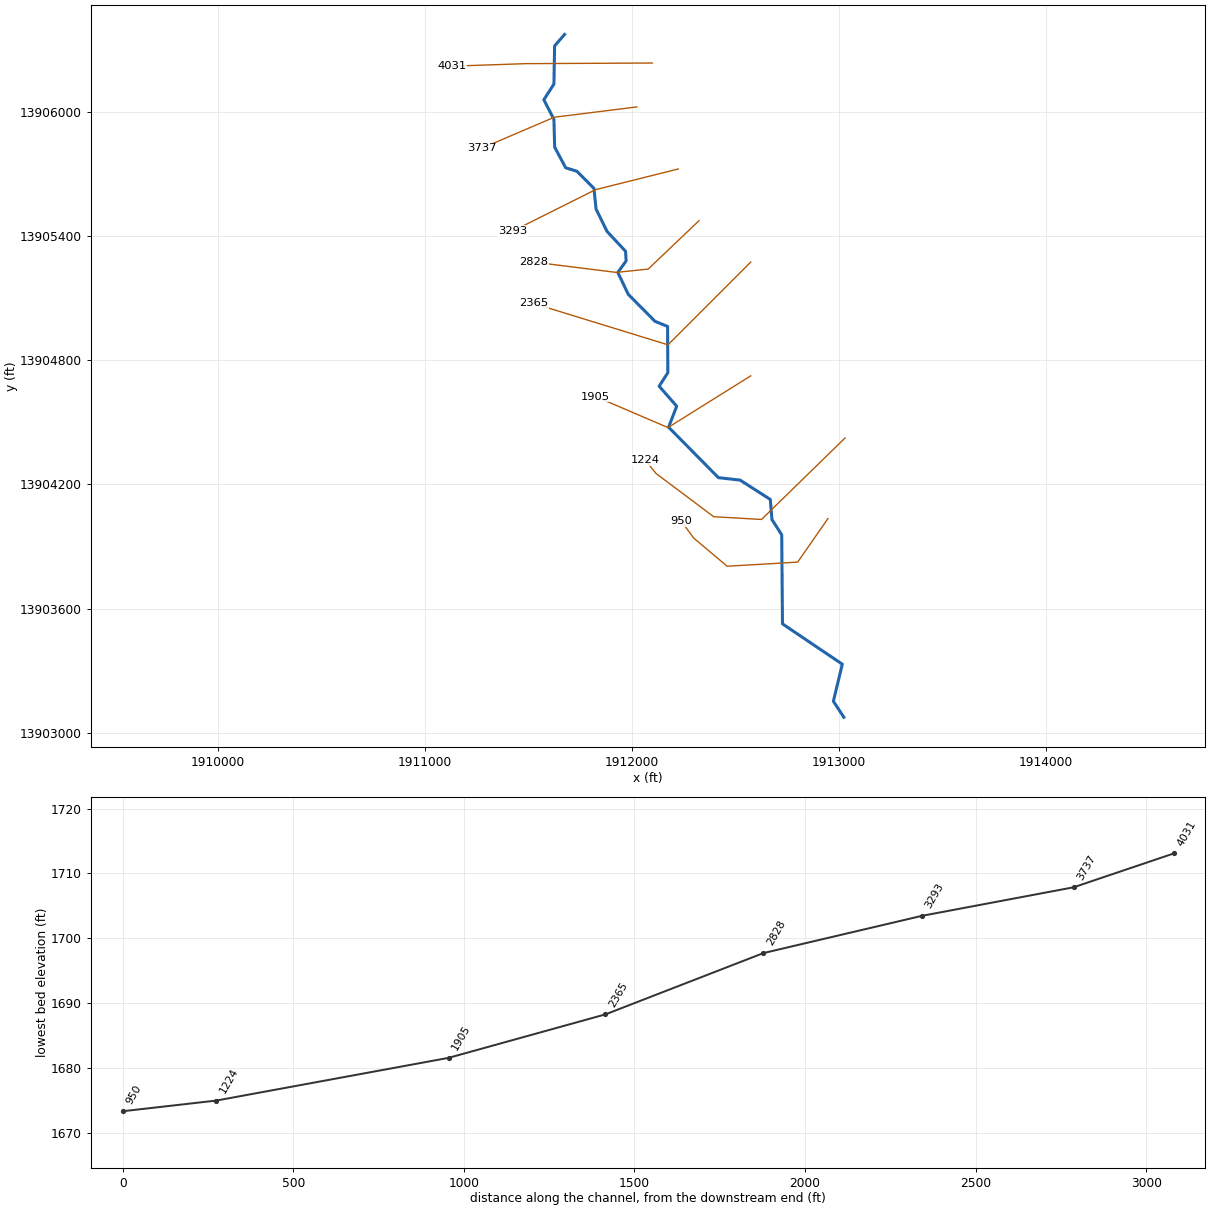
--- Marshall Creek.prj (project) ---

Proj Title=Marshall Creek Base Level Engineering
Current Plan=p01
Default Exp/Contr=0.3,0.1
English Units
Geom File=g01
Flow File=f01
Plan File=p01
BEGIN DESCRIPTION:
Marshall Creek
END DESCRIPTION:

--- Marshall Creek.p01 (plan) ---

Plan Title=Multiple Run
Short Identifier=Multiple
Geom File=g01
Flow File=f01
Subcritical Flow
K Sum by GR= 0
Std Step Tol= 0.01
Critical Tol= 0.01
Num of Std Step Trials= 20
Max Error Tol= 0.3
Flow Tol Ratio= 0.001
Split Flow NTrial= 30
Split Flow Tol= 0.02
Split Flow Ratio= 0.02
Log Output Level= 0
Friction Slope Method= 1
Unsteady Friction Slope Method= 2
Unsteady Bridges Friction Slope Method= 1
Parabolic Critical Depth
Global Vel Dist=  1 , 1 , 1
Global Log Level= 0
CheckData=True
Encroach Param= -1, 0, 0, 0
BEGIN DESCRIPTION:
Multiple Run
END DESCRIPTION:

--- Marshall Creek.f01 (steady flow) ---

Flow Title=Multiple
Number of Profiles=7
Profile Names=10-year,25-year,50-year,1pct_min,100-year,1pct_plu,500-year
River Rch & RM= Marshall Creek,Reach-1,4031
    1621    2822    3987    2721    5429   10833    9947
Boundary for River Rch & Prof#=Marshall Creek,Reach-1,1
Up Type=0
Dn Type=3
Dn Slope=0.005
Boundary for River Rch & Prof#=Marshall Creek,Reach-1,2
Up Type=0
Dn Type=3
Dn Slope=0.005
Boundary for River Rch & Prof#=Marshall Creek,Reach-1,3
Up Type=0
Dn Type=3
Dn Slope=0.005
Boundary for River Rch & Prof#=Marshall Creek,Reach-1,4
Up Type=0
Dn Type=3
Dn Slope=0.005
Boundary for River Rch & Prof#=Marshall Creek,Reach-1,5
Up Type=0
Dn Type=3
Dn Slope=0.005
Boundary for River Rch & Prof#=Marshall Creek,Reach-1,6
Up Type=0
Dn Type=3
Dn Slope=0.005
Boundary for River Rch & Prof#=Marshall Creek,Reach-1,7
Up Type=0
Dn Type=3
Dn Slope=0.005

--- Marshall Creek.g01 (geometry) ---

Geom Title=Existing Conditions

River Reach=Marshall Creek,Reach-1
Reach XY= 30
      1911675.00     13906375.00      1911627.00     13906319.63
      1911623.76     13906135.50      1911575.09     13906059.61
      1911623.75     13905964.50      1911627.35     13905830.50
      1911680.59     13905730.61      1911734.44     13905714.12
      1911817.14     13905631.19      1911827.33     13905530.97
      1911880.85     13905422.71      1911969.87     13905327.28
      1911972.90     13905280.64      1911932.56     13905225.00
      1911983.12     13905118.95      1912112.05     13904988.74
      1912173.15     13904963.86      1912174.34     13904740.16
      1912132.34     13904674.90      1912217.15     13904578.41
      1912178.16     13904476.65      1912418.83     13904232.86
      1912523.42     13904221.17      1912669.58     13904127.68
      1912677.47     13904030.57      1912724.79     13903956.73
      1912728.45     13903526.25      1913017.64     13903331.34
      1912974.44     13903152.25      1913025.00     13903075.00

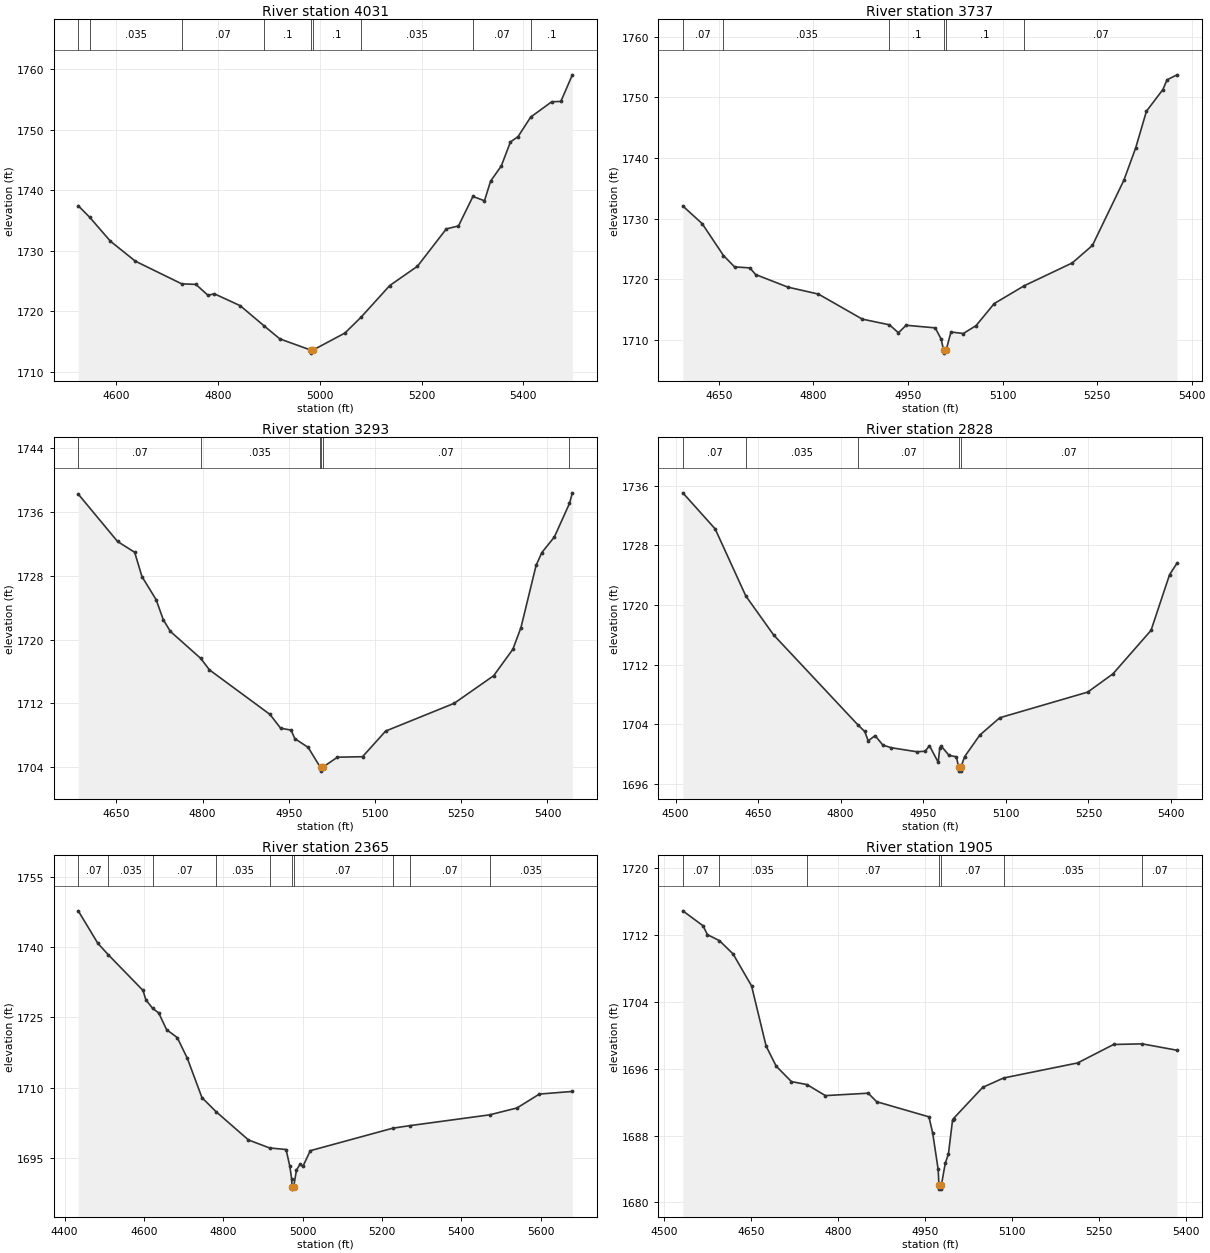
Type RM Length L Ch R = 1,4031,294,294,294
BEGIN DESCRIPTION:
Marshall Creek 6.0
END DESCRIPTION:
XS GIS Cut Line= 3
      1912099.64     13906237.08      1911489.32     13906234.07
      1911128.86     13906221.89
#Sta/Elev= 30
  4525.3 1737.44  4547.7 1735.54  4588.5 1731.58  4637.5 1728.28  4728.5 1724.54
  4756.5 1724.44  4780.5 1722.63  4792.5 1722.90  4843.5 1720.93  4891.3 1717.54
  4921.5 1715.44  4982.4 1713.59  4982.7 1713.09  4986.5 1713.59  5049.5 1716.42
  5081.1 1719.03  5137.5 1724.26  5191.9 1727.44  5248.6 1733.61  5272.5 1734.10
  5300.9 1738.97  5323.6 1738.26  5335.6 1741.50  5356.6 1744.00  5374.6 1747.97
  5389.6 1748.86  5414.4 1752.08  5455.7 1754.61  5473.7 1754.67  5496.3 1759.06
#Mann=9,-1,0
  4525.3    0.07       0  4547.7   0.035       0  4728.5    0.07       0
  4891.3     0.1       0  4982.4    0.05       0  4986.5     0.1       0
  5081.1   0.035       0  5300.9    0.07       0  5414.4     0.1       0
Bank Sta=4982.4,4986.5
Exp/Cntr=0.3,0.1

Type RM Length L Ch R = 1,3737,444,444,444
BEGIN DESCRIPTION:
Marshall Creek 5.0
END DESCRIPTION:
XS GIS Cut Line= 3
      1912024.96     13906024.99      1911625.00     13905975.00
      1911274.96     13905824.98
#Sta/Elev= 30
  4592.8 1732.10  4623.5 1729.19  4657.3 1723.94  4674.9 1722.07  4699.1 1721.91
  4708.3 1720.81  4759.4 1718.74  4808.0 1717.59  4877.5 1713.47  4920.6 1712.53
  4934.9 1711.22  4947.0 1712.46  4993.2 1712.03  5002.7 1710.17  5006.4 1708.37
  5006.6 1707.87  5010.5 1708.37  5018.2 1711.35  5037.8 1711.10  5058.0 1712.40
  5086.8 1716.03  5134.3 1718.96  5210.7 1722.73  5242.6 1725.61  5292.4 1736.32
  5311.2 1741.66  5328.3 1747.71  5354.4 1751.28  5360.9 1752.87  5376.7 1753.70
#Mann=6,-1,0
  4592.8    0.07       0  4657.3   0.035       0  4920.6     0.1       0
  5006.4    0.05       0  5010.5     0.1       0  5134.3    0.07       0
Bank Sta=5006.4,5010.5
Exp/Cntr=0.3,0.1

Type RM Length L Ch R = 1,3293,465,465,465
BEGIN DESCRIPTION:
Marshall Creek 4.0
END DESCRIPTION:
XS GIS Cut Line= 3
      1912224.96     13905724.99      1911825.00     13905625.00
      1911424.98     13905424.99
#Sta/Elev= 30
  4583.8 1738.26  4652.2 1732.31  4681.9 1730.96  4694.6 1727.91  4719.3 1725.00
  4731.7 1722.49  4744.1 1721.02  4796.9 1717.63  4812.1 1716.19  4917.3 1710.60
  4935.8 1708.87  4954.0 1708.63  4960.5 1707.56  4983.7 1706.46  5004.4 1704.02
  5005.2 1703.98  5005.5 1703.48  5009.3 1703.98  5034.7 1705.23  5078.3 1705.29
  5118.5 1708.51  5237.6 1711.99  5306.4 1715.46  5339.9 1718.79  5353.9 1721.51
  5380.2 1729.31  5390.2 1730.92  5412.0 1732.88  5438.3 1737.09  5443.3 1738.42
#Mann=6,-1,0
  4583.8    0.07       0  4796.9   0.035       0  5004.4    0.07       0
  5005.2   0.035       0  5009.3    0.07       0  5438.3   0.035       0
Bank Sta=5005.2,5009.3
Exp/Cntr=0.3,0.1

Type RM Length L Ch R = 1,2828,463,463,463
BEGIN DESCRIPTION:
Marshall Creek 3.0
END DESCRIPTION:
XS GIS Cut Line= 4
      1912325.02     13905475.02      1912079.39     13905241.08
      1911925.00     13905225.00      1911525.04     13905274.99
#Sta/Elev= 30
  4513.3 1735.03  4572.0 1730.20  4627.7 1721.21  4678.2 1715.99  4831.5 1703.92
  4843.7 1703.05  4850.0 1701.80  4862.5 1702.50  4876.6 1701.23  4892.2 1700.87
  4937.9 1700.34  4953.1 1700.40  4961.3 1701.14  4977.1 1698.93  4980.1 1700.90
  4983.1 1701.06  4996.8 1699.85  5010.3 1699.66  5014.2 1698.24  5014.5 1697.74
  5018.2 1697.74  5018.4 1698.24  5025.0 1699.67  5052.6 1702.56  5088.9 1704.89
  5248.7 1708.33  5294.6 1710.78  5363.7 1716.60  5397.3 1724.05  5410.8 1725.60
#Mann=5,-1,0
  4513.3    0.07       0  4627.7   0.035       0  4831.5    0.07       0
  5014.2    0.05       0  5018.4    0.07       0
Bank Sta=5014.2,5018.4
Exp/Cntr=0.3,0.1

Type RM Length L Ch R = 1,2365,460,460,460
BEGIN DESCRIPTION:
Marshall Creek 2.0
END DESCRIPTION:
XS GIS Cut Line= 3
      1912575.01     13905275.01      1912175.00     13904875.00
      1911524.97     13905075.01
#Sta/Elev= 30
  4434.5 1747.73  4484.0 1740.78  4510.6 1738.32  4597.9 1730.72  4604.9 1728.74
  4621.9 1726.92  4637.4 1725.92  4657.3 1722.35  4684.1 1720.67  4709.6 1716.22
  4746.4 1707.84  4782.0 1704.84  4863.7 1698.80  4917.0 1697.09  4958.5 1696.76
  4967.7 1693.28  4972.6 1690.45  4973.4 1688.80  4973.7 1688.30  4977.6 1688.80
  4984.7 1692.38  4993.8 1693.63  5000.8 1693.14  5019.6 1696.51  5227.4 1701.31
  5269.9 1701.85  5471.4 1704.16  5540.6 1705.63  5597.1 1708.60  5680.3 1709.16
#Mann=10,-1,0
  4434.5    0.07       0  4510.6   0.035       0  4621.9    0.07       0
  4782.0   0.035       0  4917.0    0.07       0  4973.4    0.05       0
  4977.6    0.07       0  5227.4   0.035       0  5269.9    0.07       0
  5471.4   0.035       0
Bank Sta=4973.4,4977.6
Exp/Cntr=0.3,0.1

Type RM Length L Ch R = 1,1905,681,681,681
BEGIN DESCRIPTION:
Marshall Creek 1.0
END DESCRIPTION:
XS GIS Cut Line= 3
      1912575.01     13904725.01      1912175.00     13904475.00
      1911825.00     13904625.00
#Sta/Elev= 30
  4531.9 1714.90  4566.8 1713.11  4574.3 1712.05  4595.1 1711.33  4618.6 1709.74
  4650.5 1705.91  4675.6 1698.71  4692.9 1696.32  4719.2 1694.47  4746.0 1694.11
  4777.9 1692.79  4851.7 1693.08  4866.3 1692.06  4956.5 1690.25  4963.0 1688.30
  4972.4 1683.96  4973.8 1682.10  4974.1 1681.60  4977.8 1681.60  4978.0 1682.10
  4984.8 1684.74  4990.1 1685.80  4997.2 1689.84  4998.9 1690.05  5049.3 1693.78
  5085.4 1694.90  5213.1 1696.70  5275.1 1698.91  5324.6 1698.98  5384.4 1698.22
#Mann=7,-1,0
  4531.9    0.07       0  4595.1   0.035       0  4746.0    0.07       0
  4973.8    0.05       0  4978.0    0.07       0  5085.4   0.035       0
  5324.6    0.07       0
Bank Sta=4973.8,4978
Exp/Cntr=0.3,0.1

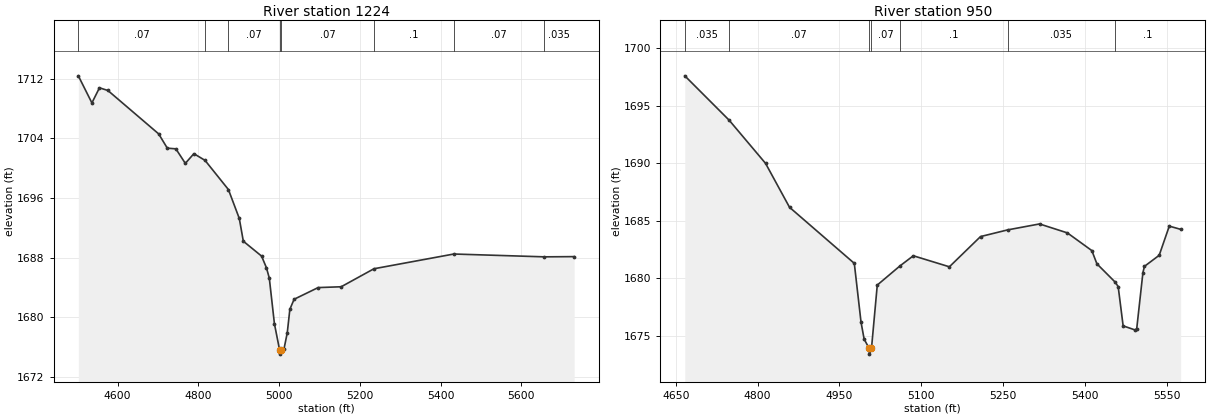
Type RM Length L Ch R = 1,1224,274,274,274
BEGIN DESCRIPTION:
Marshall Creek 0.0
END DESCRIPTION:
XS GIS Cut Line= 5
      1913030.88     13904424.64      1912627.14     13904030.85
      1912395.96     13904044.23      1912117.34     13904253.02
      1912064.86     13904318.45
#Sta/Elev= 30
  4503.0 1712.41  4536.6 1708.77  4555.3 1710.80  4576.2 1710.44  4701.9 1704.61
  4723.3 1702.69  4744.5 1702.60  4767.9 1700.65  4789.1 1701.95  4816.7 1701.05
  4874.6 1697.13  4901.5 1693.25  4911.5 1690.19  4956.7 1688.19  4968.6 1686.64
  4975.8 1685.24  4988.5 1679.10  5001.5 1675.52  5001.8 1675.02  5005.8 1675.52
  5012.1 1675.69  5020.3 1677.89  5026.7 1681.04  5037.2 1682.39  5096.7 1683.96
  5153.8 1684.07  5234.9 1686.49  5432.7 1688.47  5656.8 1688.09  5730.6 1688.12
#Mann=8,-1,0
  4503.0    0.07       0  4816.7   0.035       0  4874.6    0.07       0
  5001.5    0.05       0  5005.8    0.07       0  5234.9     0.1       0
  5432.7    0.07       0  5656.8   0.035       0
Bank Sta=5001.5,5005.8
Exp/Cntr=0.3,0.1

Type RM Length L Ch R = 1,950,0,0,0
BEGIN DESCRIPTION:
Marshall Creek 0.1
END DESCRIPTION:
XS GIS Cut Line= 5
      1912948.17     13904035.15      1912801.86     13903824.68
      1912461.10     13903804.87      1912299.63     13903940.52
      1912240.05     13904021.51
#Sta/Elev= 30
  4666.7 1697.60  4748.0 1693.74  4814.8 1689.98  4858.7 1686.16  4977.5 1681.28
  4989.8 1676.17  4995.5 1674.69  5004.7 1673.88  5005.0 1673.38  5009.0 1673.88
  5019.6 1679.39  5061.3 1681.06  5085.7 1681.94  5151.8 1680.98  5208.9 1683.61
  5258.4 1684.19  5317.1 1684.71  5368.2 1683.93  5413.0 1682.39  5422.3 1681.24
  5455.5 1679.66  5461.3 1679.26  5470.4 1675.84  5492.5 1675.48  5495.3 1675.59
  5506.7 1680.48  5509.5 1681.02  5536.5 1681.98  5555.0 1684.52  5575.8 1684.24
#Mann=7,-1,0
  4666.7   0.035       0  4748.0    0.07       0  5004.7    0.05       0
  5009.0    0.07       0  5061.3     0.1       0  5258.4   0.035       0
  5455.5     0.1       0
Bank Sta=5004.7,5009
Exp/Cntr=0.3,0.1

Chan Stop Cuts=-1