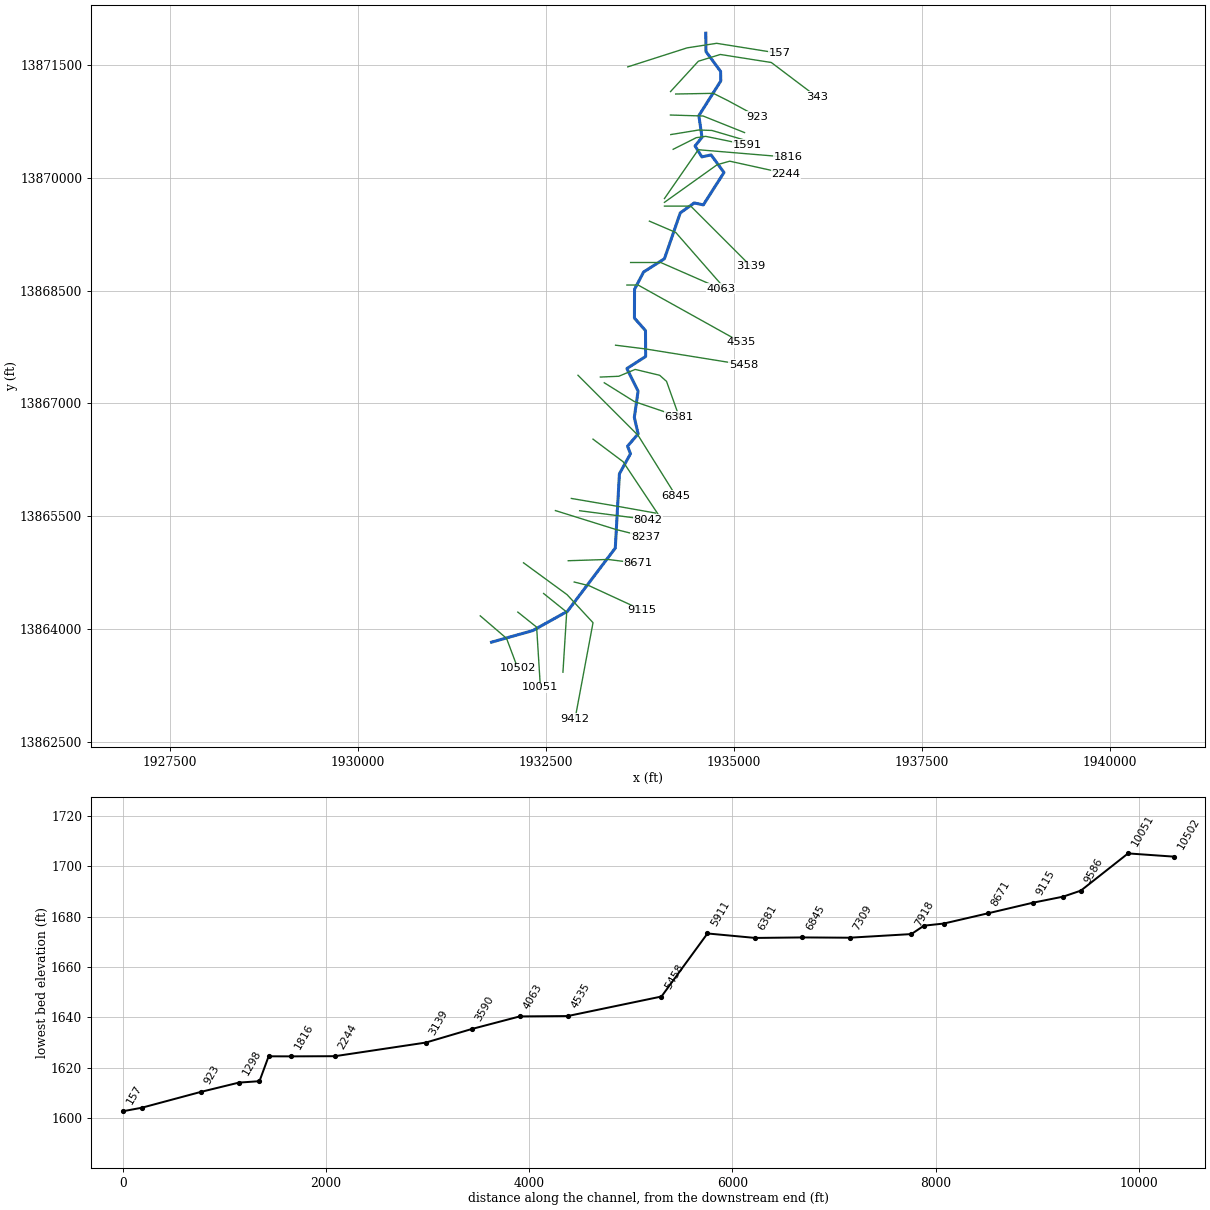
--- Mico Creek.prj (project) ---

Proj Title=Mico Creek Base Level Engineering
Current Plan=p01
Default Exp/Contr=0.3,0.1
English Units
Geom File=g01
Flow File=f01
Plan File=p01
BEGIN DESCRIPTION:
Mico Creek
END DESCRIPTION:

--- Mico Creek.p01 (plan) ---

Plan Title=Multiple Run
Short Identifier=Multiple
Geom File=g01
Flow File=f01
Subcritical Flow
K Sum by GR= 0
Std Step Tol= 0.01
Critical Tol= 0.01
Num of Std Step Trials= 20
Max Error Tol= 0.3
Flow Tol Ratio= 0.001
Split Flow NTrial= 30
Split Flow Tol= 0.02
Split Flow Ratio= 0.02
Log Output Level= 0
Friction Slope Method= 1
Unsteady Friction Slope Method= 2
Unsteady Bridges Friction Slope Method= 1
Parabolic Critical Depth
Global Vel Dist=  1 , 1 , 1
Global Log Level= 0
CheckData=True
Encroach Param= -1, 0, 0, 0
BEGIN DESCRIPTION:
Multiple Run
END DESCRIPTION:

--- Mico Creek.f01 (steady flow) ---

Flow Title=Multiple
Number of Profiles=7
Profile Names=10-year,25-year,50-year,1pct_min,100-year,1pct_plu,500-year
River Rch & RM= Mico Creek,Reach-1,10502
    2309    4071    5805    3995    7972   15906   14848
River Rch & RM= Mico Creek,Reach-1,5458
    3601    6485    9379    6535   13040   26018   24911
River Rch & RM= Mico Creek,Reach-1,3590
    4038    7293   10567    7372   14709   29347   28167
Boundary for River Rch & Prof#=Mico Creek,Reach-1,1
Up Type=0
Dn Type=3
Dn Slope=0.005
Boundary for River Rch & Prof#=Mico Creek,Reach-1,2
Up Type=0
Dn Type=3
Dn Slope=0.005
Boundary for River Rch & Prof#=Mico Creek,Reach-1,3
Up Type=0
Dn Type=3
Dn Slope=0.005
Boundary for River Rch & Prof#=Mico Creek,Reach-1,4
Up Type=0
Dn Type=3
Dn Slope=0.005
Boundary for River Rch & Prof#=Mico Creek,Reach-1,5
Up Type=0
Dn Type=3
Dn Slope=0.005
Boundary for River Rch & Prof#=Mico Creek,Reach-1,6
Up Type=0
Dn Type=3
Dn Slope=0.005
Boundary for River Rch & Prof#=Mico Creek,Reach-1,7
Up Type=0
Dn Type=3
Dn Slope=0.005

--- Mico Creek.g01 (geometry) ---

Geom Title=Existing Conditions

River Reach=Mico Creek,Reach-1
Reach XY= 30
      1931775.00     13863825.00      1932323.44     13863978.76
      1932785.00     13864235.65      1933421.25     13865076.55
      1933476.22     13866064.50      1933623.33     13866331.05
      1933584.15     13866431.73      1933725.06     13866594.99
      1933674.55     13866814.81      1933724.40     13867164.38
      1933575.59     13867464.39      1933825.00     13867625.00
      1933822.94     13867969.15      1933676.05     13868135.43
      1933677.24     13868519.07      1933797.99     13868748.52
      1934075.00     13868925.00      1934285.63     13869535.00
      1934471.60     13869667.17      1934592.02     13869641.15
      1934867.17     13870071.78      1934695.51     13870305.89
      1934572.46     13870280.01      1934482.30     13870425.08
      1934574.61     13870540.16      1934532.81     13870828.41
      1934824.52     13871290.23      1934821.92     13871416.69
      1934627.24     13871680.93      1934625.00     13871925.00

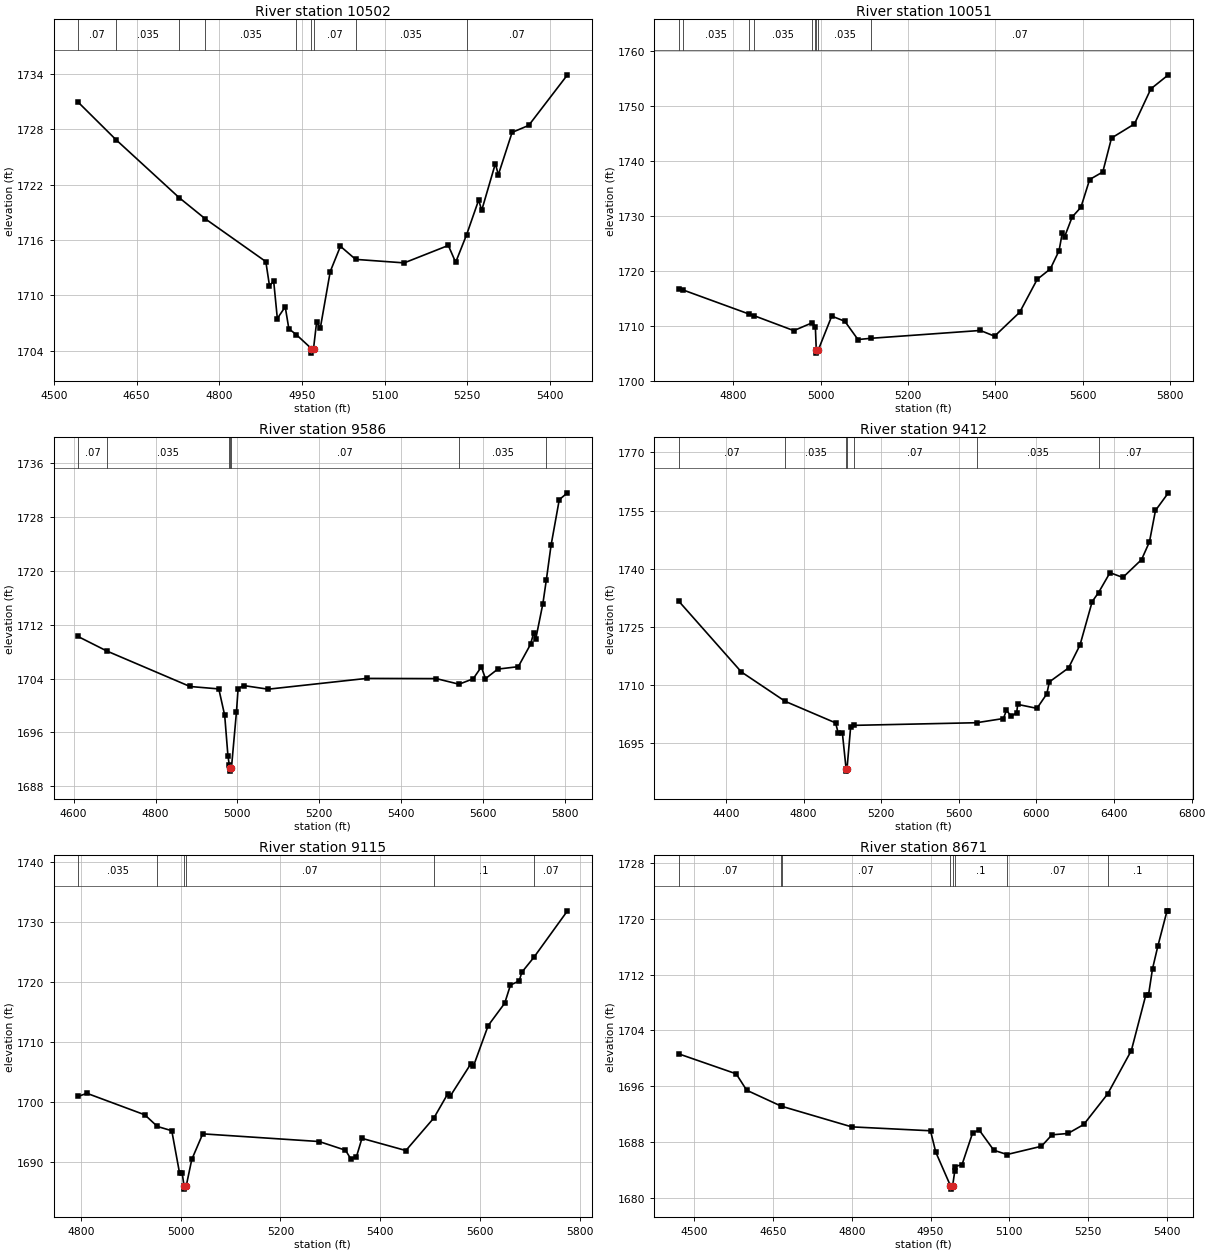
Type RM Length L Ch R = 1,10502,451,451,451
BEGIN DESCRIPTION:
Mico Creek 21.0
END DESCRIPTION:
XS GIS Cut Line= 3
      1931624.96     13864175.03      1931975.00     13863875.00
      1932124.99     13863475.02
#Sta/Elev= 30
  4543.8 1730.94  4612.7 1726.86  4727.1 1720.59  4774.4 1718.30  4884.6 1713.65
  4891.2 1711.05  4898.9 1711.51  4905.5 1707.48  4919.8 1708.75  4926.4 1706.37
  4940.0 1705.73  4967.2 1704.23  4967.4 1703.73  4971.2 1704.23  4976.8 1707.11
  4983.4 1706.42  5001.5 1712.57  5020.0 1715.31  5047.6 1713.89  5135.7 1713.51
  5215.8 1715.40  5229.1 1713.57  5249.0 1716.57  5270.9 1720.33  5276.3 1719.19
  5301.2 1724.28  5306.5 1723.05  5331.5 1727.65  5361.7 1728.41  5432.0 1733.89
#Mann=9,-1,0
  4543.8    0.07       0  4612.7   0.035       0  4727.1    0.07       0
  4774.4   0.035       0  4940.0    0.07       0  4967.2    0.05       0
  4971.2    0.07       0  5047.6   0.035       0  5249.0    0.07       0
Bank Sta=4967.2,4971.2
Exp/Cntr=0.3,0.1

Type RM Length L Ch R = 1,10051,465,465,465
BEGIN DESCRIPTION:
Mico Creek 20.0
END DESCRIPTION:
XS GIS Cut Line= 3
      1932124.97     13864225.02      1932375.00     13864025.00
      1932425.00     13863224.96
#Sta/Elev= 30
  4674.9 1716.62  4685.2 1716.47  4836.2 1712.10  4847.0 1711.82  4938.3 1709.10
  4981.1 1710.55  4987.7 1709.75  4989.8 1705.51  4990.0 1705.01  4994.0 1705.51
  5025.2 1711.74  5055.2 1710.80  5085.3 1707.48  5115.7 1707.71  5365.8 1709.13
  5398.4 1708.09  5456.0 1712.44  5496.1 1718.42  5526.1 1720.31  5546.2 1723.63
  5553.7 1726.92  5558.7 1726.12  5576.2 1729.75  5596.3 1731.52  5616.3 1736.57
  5646.4 1737.94  5666.4 1744.11  5719.0 1746.67  5756.6 1753.05  5796.7 1755.60
#Mann=9,-1,0
  4674.9    0.07       0  4685.2   0.035       0  4836.2    0.07       0
  4847.0   0.035       0  4981.1    0.07       0  4987.7   0.035       0
  4989.8   0.035       0  4994.0   0.035       0  5115.7    0.07       0
Bank Sta=4989.8,4994
Exp/Cntr=0.3,0.1

Type RM Length L Ch R = 1,9586,174,174,174
BEGIN DESCRIPTION:
Mico Creek 19.0
END DESCRIPTION:
XS GIS Cut Line= 3
      1932467.86     13864472.34      1932775.00     13864225.00
      1932725.00     13863425.01
#Sta/Elev= 30
  4610.6 1710.24  4681.2 1708.08  4884.2 1702.82  4954.6 1702.46  4969.0 1698.53
  4976.9 1692.54  4980.2 1691.17  4981.2 1690.76  4981.5 1690.26  4985.5 1690.76
  4997.8 1699.10  5001.7 1702.48  5015.0 1702.96  5075.1 1702.42  5315.6 1704.02
  5485.9 1703.99  5541.5 1703.16  5576.1 1703.96  5596.1 1705.73  5606.1 1703.98
  5636.2 1705.40  5686.3 1705.76  5716.3 1709.08  5723.9 1710.79  5728.9 1709.84
  5746.4 1715.11  5754.8 1718.61  5766.4 1723.78  5786.5 1730.55  5806.5 1731.56
#Mann=7,-1,0
  4610.6    0.07       0  4681.2   0.035       0  4980.2    0.07       0
  4981.2    0.05       0  4985.5    0.07       0  5541.5   0.035       0
  5754.8     0.1       0
Bank Sta=4981.2,4985.5
Exp/Cntr=0.3,0.1

Type RM Length L Ch R = 1,9412,297,297,297
BEGIN DESCRIPTION:
Mapping XS a916c957
END DESCRIPTION:
XS GIS Cut Line= 4
      1932200.69     13864880.31      1932780.00     13864456.69
      1933125.06     13864083.92      1932886.97     13862809.30
#Sta/Elev= 30
  4157.6 1731.62  4479.4 1713.43  4705.6 1705.85  4964.9 1700.31  4979.0 1697.64
  5000.2 1697.61  5019.4 1688.38  5019.7 1687.88  5023.7 1688.38  5042.5 1699.16
  5059.5 1699.67  5691.7 1700.35  5829.7 1701.43  5845.7 1703.55  5870.4 1701.98
  5898.4 1702.96  5903.5 1705.07  6002.7 1704.05  6053.5 1707.77  6066.6 1710.86
  6165.5 1714.46  6224.6 1720.37  6287.5 1731.56  6320.4 1733.89  6379.1 1739.00
  6445.4 1737.77  6541.8 1742.37  6582.5 1746.94  6613.5 1755.02  6679.9 1759.57
#Mann=7,-1,0
  4157.6    0.07       0  4705.6   0.035       0  5019.4   0.035       0
  5023.7   0.035       0  5059.5    0.07       0  5691.7   0.035       0
  6320.4    0.07       0
Bank Sta=5019.4,5023.7
Exp/Cntr=0.3,0.1

Type RM Length L Ch R = 1,9115,444,444,444
BEGIN DESCRIPTION:
Mico Creek 18.0
END DESCRIPTION:
XS GIS Cut Line= 3
      1932874.99     13864625.00      1933075.00     13864575.00
      1933779.36     13864249.97
#Sta/Elev= 30
  4793.8 1700.93  4811.8 1701.44  4927.8 1697.86  4953.0 1695.92  4981.9 1695.21
  4997.4 1688.20  5002.7 1688.20  5006.5 1685.98  5006.8 1685.48  5010.8 1685.98
  5022.0 1690.42  5044.0 1694.69  5277.6 1693.41  5330.4 1691.96  5341.0 1690.53
  5352.4 1690.89  5363.4 1693.94  5451.5 1691.91  5507.8 1697.35  5535.5 1701.35
  5541.0 1701.04  5581.4 1706.30  5586.9 1705.93  5616.7 1712.74  5649.8 1716.46
  5661.3 1719.48  5678.7 1720.16  5684.2 1721.62  5708.4 1724.11  5775.7 1731.85
#Mann=6,-1,0
  4793.8   0.035       0  4953.0    0.07       0  5006.5    0.05       0
  5010.8    0.07       0  5507.8     0.1       0  5708.4    0.07       0
Bank Sta=5006.5,5010.8
Exp/Cntr=0.3,0.1

Type RM Length L Ch R = 1,8671,434,434,434
BEGIN DESCRIPTION:
Mico Creek 17.0
END DESCRIPTION:
XS GIS Cut Line= 3
      1932795.95     13864908.21      1933325.00     13864925.00
      1933724.97     13864875.00
#Sta/Elev= 30
  4470.7 1700.64  4579.8 1697.79  4599.8 1695.44  4665.8 1693.15  4667.3 1693.12
  4799.9 1690.19  4950.0 1689.63  4960.0 1686.57  4987.9 1681.77  4988.2 1681.27
  4992.2 1681.77  4996.2 1683.84  4997.5 1684.51  5010.1 1684.79  5030.3 1689.34
  5042.8 1689.73  5070.6 1686.84  5095.8 1686.23  5161.3 1687.41  5181.4 1689.05
  5211.7 1689.24  5241.9 1690.53  5287.4 1694.90  5332.6 1701.13  5360.3 1709.12
  5365.3 1709.08  5372.9 1712.83  5383.0 1716.06  5400.6 1721.14  5403.1 1721.14
#Mann=8,-1,0
  4470.7    0.07       0  4665.8   0.035       0  4667.3    0.07       0
  4987.9    0.05       0  4992.2    0.07       0  4996.2     0.1       0
  5095.8    0.07       0  5287.4     0.1       0
Bank Sta=4987.9,4992.2
Exp/Cntr=0.3,0.1

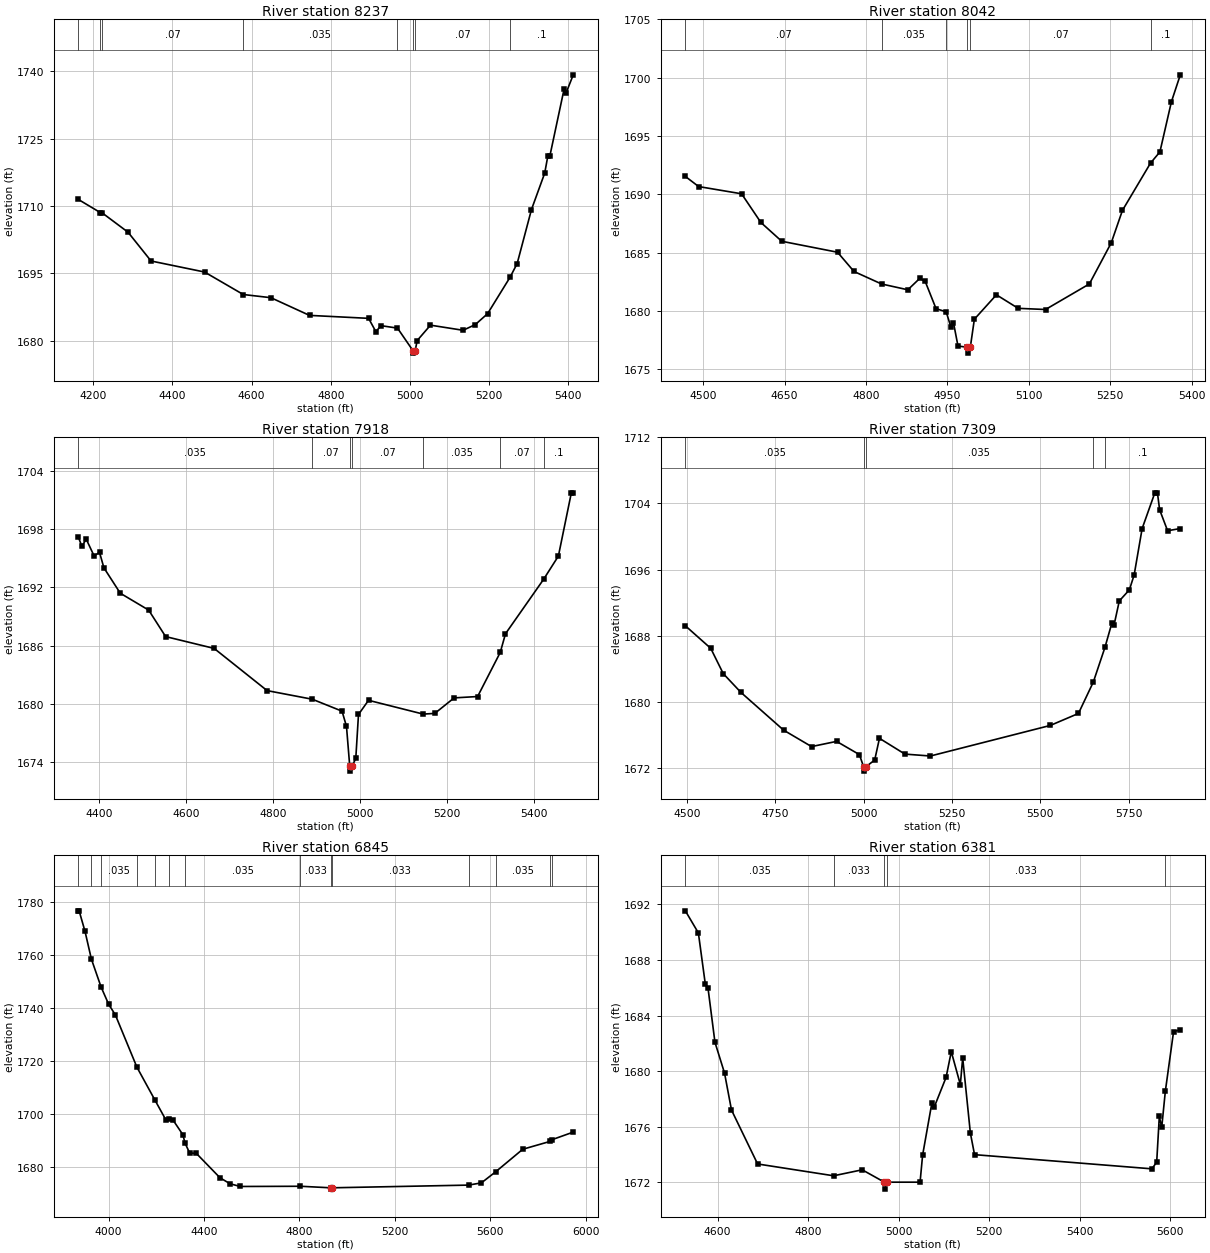
Type RM Length L Ch R = 1,8237,195,195,195
BEGIN DESCRIPTION:
Mico Creek 16.0
END DESCRIPTION:
XS GIS Cut Line= 3
      1932625.03     13865574.99      1933425.00     13865325.00
      1933824.97     13865225.01
#Sta/Elev= 30
  4162.3 1711.47  4217.7 1708.55  4223.2 1708.43  4288.0 1704.16  4346.1 1697.75
  4481.3 1695.29  4579.1 1690.28  4648.9 1689.57  4746.4 1685.63  4895.7 1684.97
  4914.0 1682.01  4927.1 1683.34  4968.7 1682.79  5008.2 1677.72  5008.6 1677.22
  5013.2 1677.72  5018.5 1680.03  5052.0 1683.45  5134.4 1682.31  5165.3 1683.58
  5196.3 1686.01  5252.8 1694.09  5271.0 1697.18  5307.1 1709.20  5340.6 1717.33
  5348.3 1721.05  5353.5 1721.10  5389.5 1736.03  5394.7 1735.22  5412.7 1739.23
#Mann=8,-1,0
  4162.3    0.07       0  4217.7     0.1       0  4223.2    0.07       0
  4579.1   0.035       0  4968.7    0.07       0  5008.2    0.05       0
  5013.2    0.07       0  5252.8     0.1       0
Bank Sta=5008.2,5013.2
Exp/Cntr=0.3,0.1

Type RM Length L Ch R = 1,8042,124,124,124
BEGIN DESCRIPTION:
Mapping XS 6bcbf049
END DESCRIPTION:
XS GIS Cut Line= 2
      1932946.94     13865573.32      1933851.21     13865455.67
#Sta/Elev= 30
  4467.3 1691.53  4491.8 1690.66  4570.9 1690.04  4606.5 1687.58  4644.9 1685.97
  4747.7 1685.03  4778.0 1683.38  4828.7 1682.31  4877.2 1681.81  4899.0 1682.78
  4909.1 1682.54  4929.2 1680.19  4947.9 1679.92  4956.3 1678.64  4961.3 1678.99
  4969.6 1676.99  4987.1 1676.88  4987.5 1676.38  4992.3 1676.88  4999.8 1679.29
  5040.4 1681.38  5080.5 1680.22  5130.9 1680.12  5211.6 1682.31  5251.9 1685.83
  5272.6 1688.62  5324.3 1692.67  5341.6 1693.63  5362.8 1697.93  5379.2 1700.24
#Mann=6,-1,0
  4467.3    0.07       0  4828.7   0.035       0  4947.9    0.07       0
  4987.1    0.05       0  4992.3    0.07       0  5324.3     0.1       0
Bank Sta=4987.1,4992.3
Exp/Cntr=0.3,0.1

Type RM Length L Ch R = 1,7918,609,609,609
BEGIN DESCRIPTION:
Mico Creek 15.0
END DESCRIPTION:
XS GIS Cut Line= 3
      1932836.92     13865736.61      1933474.58     13865627.89
      1933958.63     13865541.84
#Sta/Elev= 30
  4352.7 1697.19  4360.9 1696.23  4371.0 1696.96  4389.1 1695.23  4401.5 1695.61
  4411.6 1694.01  4449.3 1691.39  4514.6 1689.65  4553.6 1686.92  4665.2 1685.70
  4787.0 1681.35  4891.1 1680.46  4959.4 1679.23  4969.6 1677.66  4977.1 1673.55
  4977.5 1673.05  4982.3 1673.55  4991.0 1674.36  4997.2 1678.89  5020.3 1680.35
  5146.0 1678.93  5172.7 1679.00  5217.2 1680.60  5271.2 1680.74  5323.3 1685.29
  5335.3 1687.21  5423.1 1692.83  5457.0 1695.22  5486.8 1701.74  5491.2 1701.74
#Mann=7,-1,0
  4352.7   0.035       0  4891.1    0.07       0  4977.1    0.05       0
  4982.3    0.07       0  5146.0   0.035       0  5323.3    0.07       0
  5423.1     0.1       0
Bank Sta=4977.1,4982.3
Exp/Cntr=0.3,0.1

Type RM Length L Ch R = 1,7309,464,464,464
BEGIN DESCRIPTION:
Mico Creek 14.0
END DESCRIPTION:
XS GIS Cut Line= 3
      1933124.97     13866525.03      1933525.00     13866225.00
      1934024.98     13865475.03
#Sta/Elev= 30
  4495.0 1689.20  4566.9 1686.47  4602.3 1683.41  4652.3 1681.14  4773.2 1676.57
  4852.3 1674.58  4923.2 1675.21  4987.8 1673.61  4999.9 1672.11  5000.4 1671.61
  5005.2 1672.11  5031.1 1672.95  5044.6 1675.58  5116.7 1673.67  5188.8 1673.44
  5528.4 1677.14  5608.0 1678.59  5650.1 1682.39  5683.0 1686.58  5702.6 1689.53
  5708.6 1689.25  5723.7 1692.21  5752.2 1693.55  5765.7 1695.35  5788.3 1700.96
  5824.3 1705.29  5831.8 1705.24  5837.8 1703.25  5860.4 1700.70  5896.4 1700.97
#Mann=5,-1,0
  4495.0   0.035       0  4999.9   0.035       0  5005.2   0.035       0
  5650.1    0.07       0  5683.0     0.1       0
Bank Sta=4999.9,5005.2
Exp/Cntr=0.3,0.1

Type RM Length L Ch R = 1,6845,464,464,464
BEGIN DESCRIPTION:
Mico Creek 13.0
END DESCRIPTION:
XS GIS Cut Line= 3
      1932925.01     13867374.99      1933725.00     13866575.00
      1934225.03     13865774.96
#Sta/Elev= 30
  3872.9 1776.84  3876.4 1776.84  3901.2 1769.04  3927.7 1758.65  3968.5 1748.05
  4000.2 1741.55  4028.4 1737.50  4118.7 1717.77  4193.6 1705.45  4240.6 1697.77
  4253.6 1698.38  4268.9 1697.96  4311.3 1692.28  4320.1 1689.16  4339.6 1685.38
  4367.9 1685.21  4466.9 1676.01  4509.3 1673.74  4551.7 1672.72  4804.2 1672.80
  4930.9 1672.22  4931.3 1671.72  4936.2 1672.22  5508.6 1673.24  5562.6 1674.08
  5622.4 1678.26  5736.0 1686.78  5849.9 1689.73  5860.1 1690.44  5947.7 1693.26
#Mann=14,-1,0
  3872.9   0.035       0  3927.7    0.07       0  3968.5   0.035       0
  4118.7    0.07       0  4193.6   0.035       0  4253.6    0.07       0
  4320.1   0.035       0  4804.2   0.033       0  4930.9   0.033       0
  4936.2   0.033       0  5508.6    0.07       0  5622.4   0.035       0
  5849.9     0.1       0  5860.1    0.07       0
Bank Sta=4930.9,4936.2
Exp/Cntr=0.3,0.1

Type RM Length L Ch R = 1,6381,470,470,470
BEGIN DESCRIPTION:
Mico Creek 12.0
END DESCRIPTION:
XS GIS Cut Line= 3
      1933275.04     13867274.97      1933675.00     13867025.00
      1934264.44     13866825.30
#Sta/Elev= 30
  4528.8 1691.54  4557.6 1689.95  4573.0 1686.25  4578.9 1685.98  4594.2 1682.09
  4615.4 1679.87  4630.8 1677.21  4688.5 1673.33  4856.5 1672.48  4919.7 1672.91
  4968.8 1672.02  4969.3 1671.52  4974.3 1672.02  5047.6 1672.02  5053.2 1673.96
  5073.7 1677.72  5079.0 1677.43  5105.1 1679.56  5116.6 1681.41  5136.6 1679.04
  5141.8 1680.96  5158.8 1675.55  5168.0 1674.00  5560.0 1672.98  5570.6 1673.46
  5576.4 1676.75  5581.7 1675.96  5589.7 1678.56  5607.9 1682.85  5622.8 1682.98
#Mann=5,-1,0
  4528.8   0.035       0  4856.5   0.033       0  4968.8   0.033       0
  4974.3   0.033       0  5589.7    0.07       0
Bank Sta=4968.8,4974.3
Exp/Cntr=0.3,0.1

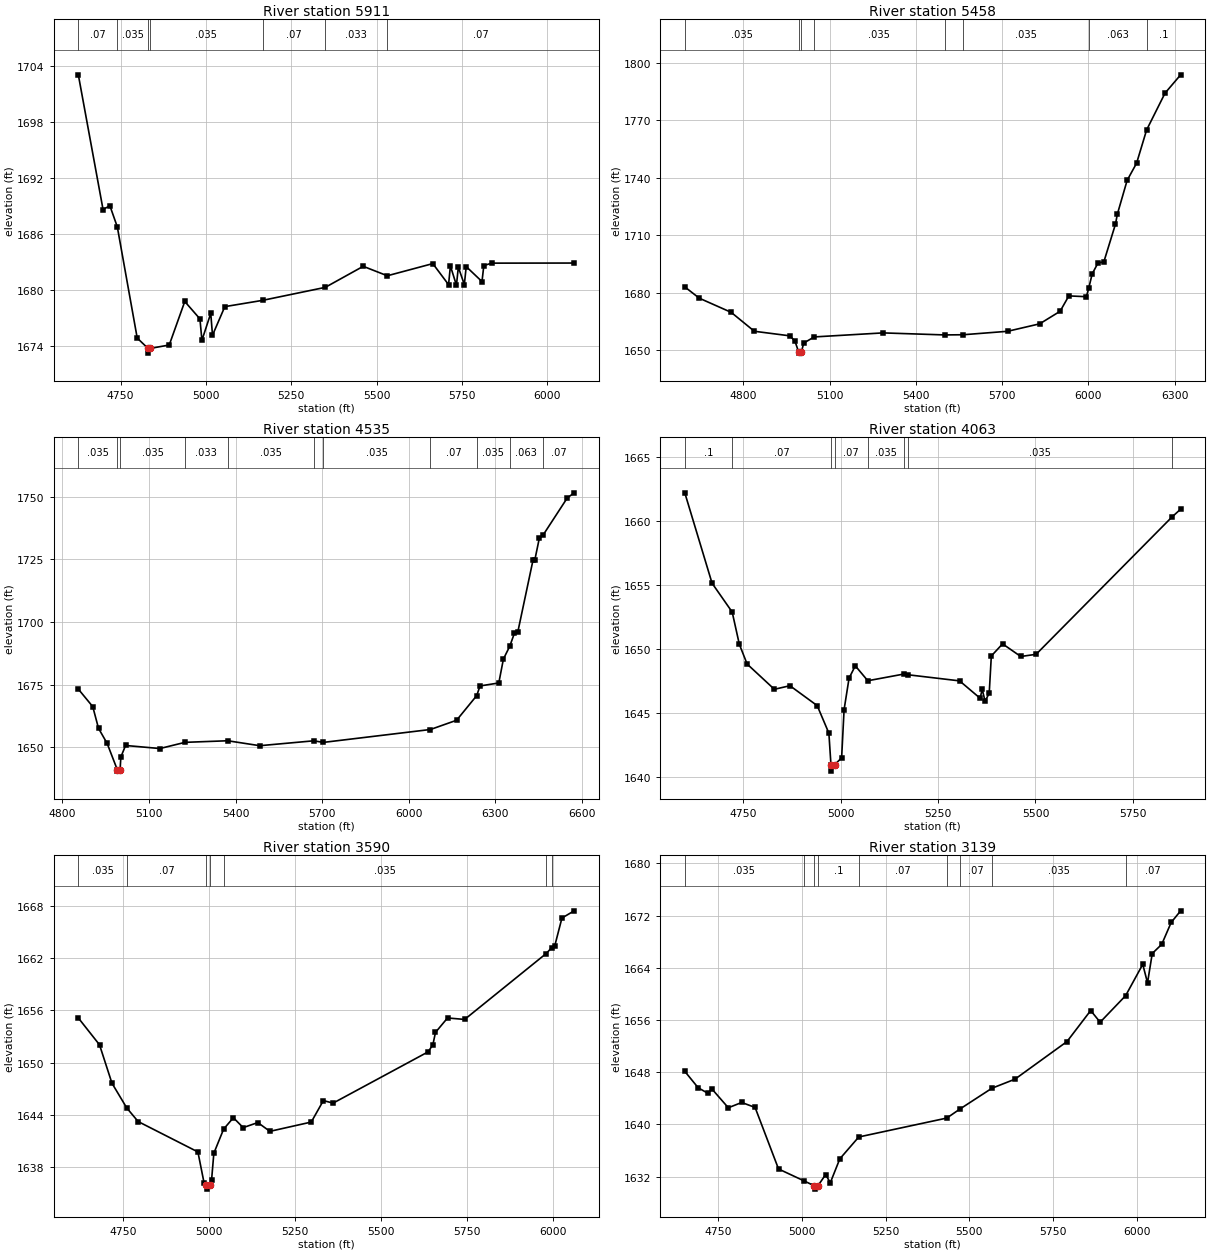
Type RM Length L Ch R = 1,5911,453,453,453
BEGIN DESCRIPTION:
Mico Creek 11.0
END DESCRIPTION:
XS GIS Cut Line= 6
      1933222.67     13867351.21      1933467.45     13867361.63
      1933686.20     13867452.78      1934011.72     13867374.65
      1934102.86     13867293.92      1934272.13     13866819.98
#Sta/Elev= 30
  4626.3 1703.04  4698.7 1688.64  4718.7 1689.05  4740.5 1686.78  4798.8 1674.90
  4830.6 1673.79  4831.0 1673.29  4836.2 1673.79  4892.6 1674.16  4938.1 1678.81
  4982.5 1676.95  4988.3 1674.66  5014.2 1677.54  5019.3 1675.20  5055.4 1678.26
  5165.9 1678.93  5349.6 1680.32  5460.8 1682.57  5531.4 1681.56  5664.6 1682.86
  5710.8 1680.61  5716.2 1682.61  5733.9 1680.55  5739.4 1682.48  5757.0 1680.62
  5762.5 1682.54  5808.7 1680.94  5814.1 1682.65  5837.2 1682.91  6078.7 1682.92
#Mann=7,-1,0
  4626.3    0.07       0  4740.5   0.035       0  4830.6   0.035       0
  4836.2   0.035       0  5165.9    0.07       0  5349.6   0.033       0
  5531.4    0.07       0
Bank Sta=4830.6,4836.2
Exp/Cntr=0.3,0.1

Type RM Length L Ch R = 1,5458,923,923,923
BEGIN DESCRIPTION:
Mico Creek 10.0
END DESCRIPTION:
XS GIS Cut Line= 3
      1933425.03     13867775.00      1933825.00     13867725.00
      1935128.56     13867515.31
#Sta/Elev= 30
  4596.9 1682.94  4647.3 1677.04  4758.1 1669.64  4838.7 1659.74  4962.2 1657.35
  4979.8 1654.57  4992.8 1648.81  4993.3 1648.31  5002.1 1648.81  5010.1 1653.55
  5046.6 1656.78  5286.0 1658.89  5499.8 1657.83  5564.0 1657.92  5719.1 1659.73
  5830.5 1663.64  5901.4 1670.20  5931.8 1678.24  5992.6 1677.82  6001.5 1682.61
  6012.8 1689.72  6033.1 1695.47  6053.4 1696.04  6093.9 1715.81  6100.4 1720.99
  6134.4 1738.67  6167.3 1747.67  6202.1 1765.04  6266.1 1784.29  6320.3 1793.86
#Mann=8,-1,0
  4596.9   0.035       0  4992.8    0.05       0  5002.1   0.035       0
  5046.6   0.035       0  5499.8    0.07       0  5564.0   0.035       0
  6001.5   0.063       0  6202.1     0.1       0
Bank Sta=4992.8,5002.1
Exp/Cntr=0.3,0.1

Type RM Length L Ch R = 1,4535,472,472,472
BEGIN DESCRIPTION:
Mico Creek 9.0
END DESCRIPTION:
XS GIS Cut Line= 3
      1933574.95     13868575.00      1933725.00     13868575.00
      1935095.93     13867811.59
#Sta/Elev= 30
  4855.0 1673.27  4905.0 1666.29  4925.0 1657.64  4955.0 1651.59  4990.3 1641.07
  4990.8 1640.57  4999.7 1641.07  5002.5 1646.22  5018.8 1650.80  5137.7 1649.58
  5225.1 1652.05  5372.9 1652.68  5484.1 1650.71  5671.2 1652.66  5704.8 1652.03
  6075.9 1657.17  6166.6 1660.86  6236.3 1670.68  6247.8 1674.54  6312.9 1675.73
  6328.9 1685.27  6351.1 1690.42  6366.7 1695.46  6378.6 1695.95  6431.8 1724.86
  6437.5 1724.61  6453.5 1733.50  6466.0 1734.62  6550.2 1749.49  6574.2 1751.55
#Mann=11,-1,0
  4855.0   0.035       0  4990.3   0.035       0  4999.7   0.035       0
  5225.1   0.033       0  5372.9   0.035       0  5671.2    0.07       0
  5704.8   0.035       0  6075.9    0.07       0  6236.3   0.035       0
  6351.1   0.063       0  6466.0    0.07       0
Bank Sta=4990.3,4999.7
Exp/Cntr=0.3,0.1

Type RM Length L Ch R = 1,4063,473,473,473
BEGIN DESCRIPTION:
Mico Creek 8.0
END DESCRIPTION:
XS GIS Cut Line= 3
      1933624.98     13868875.00      1934025.00     13868875.00
      1934824.97     13868525.01
#Sta/Elev= 30
  4599.6 1662.23  4669.6 1655.15  4721.3 1652.89  4739.6 1650.37  4759.6 1648.82
  4829.6 1646.84  4869.6 1647.12  4939.6 1645.56  4969.6 1643.40  4974.9 1640.93
  4975.4 1640.43  4984.3 1640.93  5002.3 1641.47  5008.6 1645.24  5021.4 1647.71
  5037.4 1648.68  5069.5 1647.51  5163.1 1648.04  5172.1 1647.98  5305.2 1647.50
  5357.9 1646.14  5363.3 1646.84  5370.7 1645.90  5381.3 1646.54  5386.7 1649.45
  5415.6 1650.40  5462.3 1649.41  5501.7 1649.58  5849.7 1660.31  5872.8 1660.95
#Mann=8,-1,0
  4599.6     0.1       0  4721.3    0.07       0  4974.9    0.05       0
  4984.3    0.07       0  5069.5   0.035       0  5163.1   0.033       0
  5172.1   0.035       0  5849.7    0.07       0
Bank Sta=4974.9,4984.3
Exp/Cntr=0.3,0.1

Type RM Length L Ch R = 1,3590,451,451,451
BEGIN DESCRIPTION:
Mico Creek 7.0
END DESCRIPTION:
XS GIS Cut Line= 3
      1933874.99     13869425.00      1934225.00     13869275.00
      1934924.99     13868475.01
#Sta/Elev= 30
  4618.6 1655.13  4680.3 1652.04  4716.5 1647.62  4759.7 1644.77  4792.7 1643.21
  4966.8 1639.71  4984.9 1636.11  4991.6 1635.93  4992.1 1635.43  5001.8 1635.93
  5006.5 1636.44  5013.2 1639.56  5041.7 1642.34  5070.1 1643.65  5098.6 1642.51
  5141.3 1643.09  5176.4 1642.08  5296.9 1643.15  5332.1 1645.62  5360.5 1645.33
  5637.2 1651.23  5651.0 1652.05  5658.6 1653.47  5693.7 1655.13  5743.5 1654.96
  5980.8 1662.54  5996.8 1663.21  6005.9 1663.43  6026.8 1666.63  6062.4 1667.46
#Mann=7,-1,0
  4618.6   0.035       0  4759.7    0.07       0  4991.6    0.05       0
  5001.8    0.07       0  5041.7   0.035       0  5980.8    0.07       0
  5996.8   0.035       0
Bank Sta=4991.6,5001.8
Exp/Cntr=0.3,0.1

Type RM Length L Ch R = 1,3139,895,895,895
BEGIN DESCRIPTION:
Mico Creek 6.0
END DESCRIPTION:
XS GIS Cut Line= 3
      1934075.02     13869625.00      1934425.00     13869625.00
      1935224.96     13868825.04
#Sta/Elev= 30
  4650.2 1648.12  4690.2 1645.60  4720.2 1644.73  4730.2 1645.48  4780.2 1642.54
  4820.2 1643.35  4860.2 1642.59  4930.2 1633.16  5006.2 1631.34  5037.5 1630.57
  5038.0 1630.07  5047.7 1630.57  5070.9 1632.29  5085.0 1631.06  5113.3 1634.71
  5169.9 1638.06  5432.9 1640.96  5472.3 1642.35  5567.7 1645.53  5636.6 1646.92
  5792.1 1652.69  5862.8 1657.44  5891.1 1655.65  5967.2 1659.72  6018.4 1664.52
  6032.6 1661.68  6046.7 1666.18  6075.0 1667.58  6103.3 1670.94  6131.5 1672.72
#Mann=9,-1,0
  4650.2   0.035       0  5006.2     0.1       0  5037.5   0.035       0
  5047.7     0.1       0  5169.9    0.07       0  5432.9   0.035       0
  5472.3    0.07       0  5567.7   0.035       0  5967.2    0.07       0
Bank Sta=5037.5,5047.7
Exp/Cntr=0.3,0.1

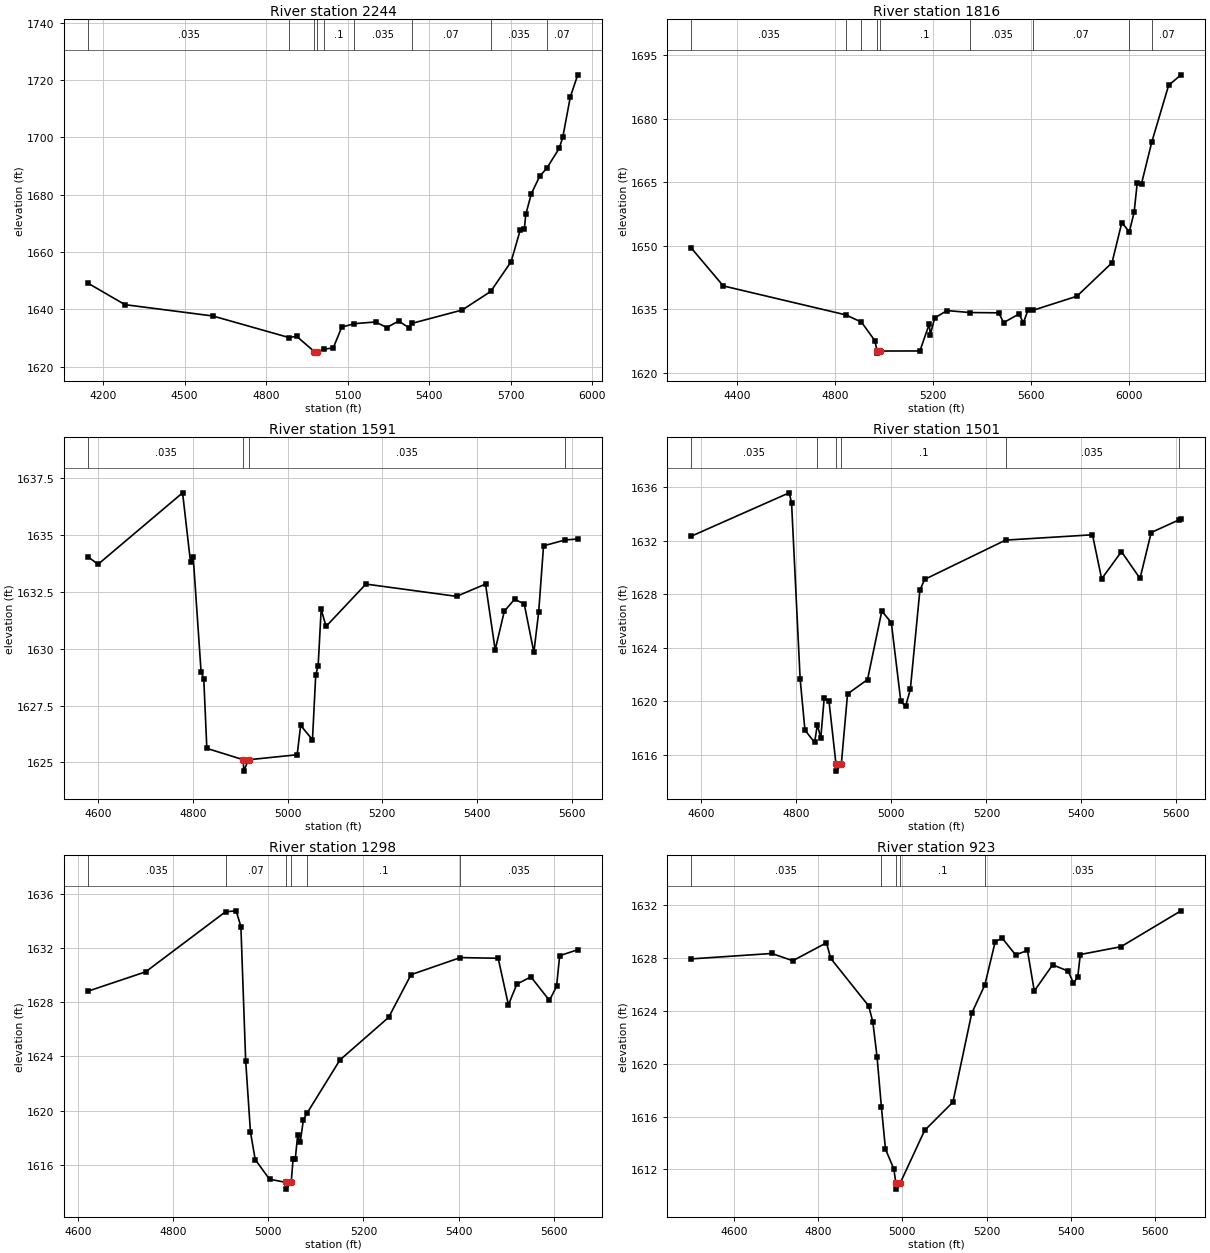
Type RM Length L Ch R = 1,2244,428,428,428
BEGIN DESCRIPTION:
Mico Creek 5.0
END DESCRIPTION:
XS GIS Cut Line= 4
      1934075.01     13869675.01      1934775.00     13870175.00
      1934943.09     13870222.65      1935691.80     13870057.69
#Sta/Elev= 30
  4145.5 1649.03  4280.7 1641.59  4603.9 1637.64  4884.2 1630.11  4912.3 1630.55
  4978.0 1625.17  4978.5 1624.67  4989.1 1625.17  5012.2 1626.01  5047.3 1626.51
  5078.5 1633.76  5125.3 1634.96  5202.9 1635.55  5244.1 1633.61  5287.8 1635.86
  5325.7 1633.54  5336.3 1635.05  5521.7 1639.72  5626.6 1646.20  5701.7 1656.58
  5735.3 1667.63  5750.6 1668.14  5755.8 1673.11  5776.3 1680.34  5807.0 1686.44
  5832.5 1689.15  5878.7 1696.14  5892.0 1700.07  5919.7 1714.14  5947.1 1721.84
#Mann=9,-1,0
  4145.5   0.035       0  4884.2    0.07       0  4978.0    0.05       0
  4989.1    0.07       0  5012.2     0.1       0  5125.3   0.035       0
  5336.3    0.07       0  5626.6   0.035       0  5832.5    0.07       0
Bank Sta=4978,4989.1
Exp/Cntr=0.3,0.1

Type RM Length L Ch R = 1,1816,225,225,225
BEGIN DESCRIPTION:
Mico Creek 4.0
END DESCRIPTION:
XS GIS Cut Line= 3
      1934075.02     13869725.03      1934525.00     13870375.00
      1935725.01     13870275.00
#Sta/Elev= 30
  4215.4 1649.39  4345.1 1640.48  4844.2 1633.64  4908.1 1631.93  4962.7 1627.56
  4972.0 1625.10  4972.5 1624.60  4983.1 1625.10  5146.4 1625.11  5184.1 1631.42
  5189.1 1628.99  5206.6 1632.92  5256.8 1634.65  5350.2 1634.19  5467.5 1634.12
  5487.6 1631.81  5550.3 1633.85  5567.9 1631.77  5587.9 1634.88  5607.2 1634.72
  5786.1 1638.04  5929.1 1645.94  5969.3 1655.46  5999.7 1653.24  6019.4 1657.89
  6032.0 1664.84  6049.5 1664.66  6091.3 1674.47  6159.9 1687.87  6210.1 1690.35
#Mann=9,-1,0
  4215.4   0.035       0  4844.2    0.07       0  4908.1     0.1       0
  4972.0    0.05       0  4983.1     0.1       0  5350.2   0.035       0
  5607.2    0.07       0  5999.7   0.035       0  6091.3    0.07       0
Bank Sta=4972,4983.1
Exp/Cntr=0.3,0.1

Type RM Length L Ch R = 1,1591,90,90,90
BEGIN DESCRIPTION:
Mapping XS 2274449a
END DESCRIPTION:
XS GIS Cut Line= 4
      1934191.33     13870380.78      1934497.44     13870534.83
      1934623.90     13870552.78      1935175.82     13870439.66
#Sta/Elev= 30
  4578.9 1634.03  4599.6 1633.71  4778.1 1636.85  4794.9 1633.79  4800.5 1634.04
  4817.2 1628.97  4822.8 1628.69  4829.3 1625.62  4906.5 1625.12  4907.0 1624.62
  4917.6 1625.12  5020.1 1625.34  5027.4 1626.63  5052.4 1626.00  5059.3 1628.85
  5064.4 1629.25  5070.8 1631.73  5081.1 1630.98  5165.3 1632.84  5356.7 1632.30
  5417.9 1632.84  5438.3 1629.95  5457.6 1631.65  5479.2 1632.17  5499.6 1631.97
  5520.0 1629.84  5530.2 1631.62  5540.4 1634.52  5586.1 1634.78  5612.7 1634.82
#Mann=4,-1,0
  4578.9   0.035       0  4906.5   0.035       0  4917.6   0.035       0
  5586.1    0.07       0
Bank Sta=4906.5,4917.6
Exp/Cntr=0.3,0.1

Type RM Length L Ch R = 1,1501,203,203,203
BEGIN DESCRIPTION:
Mapping XS 958cc011
END DESCRIPTION:
XS GIS Cut Line= 4
      1934159.23     13870576.53      1934531.61     13870637.28
      1934706.74     13870631.19      1935165.11     13870496.45
#Sta/Elev= 30
  4579.2 1632.36  4784.9 1635.60  4789.9 1634.87  4808.0 1621.66  4818.1 1617.84
  4838.4 1616.92  4844.3 1618.25  4851.4 1617.24  4858.6 1620.22  4868.8 1619.99
  4883.5 1615.27  4884.0 1614.77  4894.6 1615.27  4907.8 1620.55  4949.8 1621.62
  4979.9 1626.75  4999.9 1625.89  5019.9 1619.99  5029.9 1619.62  5039.9 1620.88
  5060.0 1628.30  5070.0 1629.12  5240.4 1632.06  5423.3 1632.46  5442.6 1629.16
  5484.3 1631.20  5523.4 1629.19  5546.9 1632.63  5605.1 1633.57  5609.5 1633.62
#Mann=6,-1,0
  4579.2   0.035       0  4844.3     0.1       0  4883.5    0.05       0
  4894.6     0.1       0  5240.4   0.035       0  5605.1    0.07       0
Bank Sta=4883.5,4894.6
Exp/Cntr=0.3,0.1

Type RM Length L Ch R = 1,1298,375,375,375
BEGIN DESCRIPTION:
Mico Creek 3.0
END DESCRIPTION:
XS GIS Cut Line= 3
      1934154.41     13870836.54      1934589.12     13870823.35
      1935140.28     13870602.97
#Sta/Elev= 30
  4621.9 1628.81  4742.5 1630.23  4910.3 1634.66  4932.6 1634.73  4942.6 1633.57
  4952.6 1623.68  4962.7 1618.41  4972.7 1616.38  5002.7 1614.93  5037.1 1614.70
  5037.6 1614.20  5048.3 1614.70  5052.2 1616.39  5056.8 1616.39  5061.8 1618.16
  5067.2 1617.65  5073.9 1619.31  5081.2 1619.78  5150.7 1623.73  5253.0 1626.87
  5300.1 1630.02  5403.7 1631.28  5483.2 1631.23  5504.7 1627.79  5522.3 1629.32
  5551.9 1629.86  5590.9 1628.12  5605.8 1629.15  5612.4 1631.42  5650.4 1631.86
#Mann=6,-1,0
  4621.9   0.035       0  4910.3    0.07       0  5037.1    0.05       0
  5048.3    0.07       0  5081.2     0.1       0  5403.7   0.035       0
Bank Sta=5037.1,5048.3
Exp/Cntr=0.3,0.1

Type RM Length L Ch R = 1,923,580,580,580
BEGIN DESCRIPTION:
Mico Creek 2.0
END DESCRIPTION:
XS GIS Cut Line= 4
      1934224.21     13871115.99      1934725.00     13871125.00
      1934925.00     13871025.00      1935310.40     13870816.22
#Sta/Elev= 30
  4498.9 1627.95  4689.7 1628.36  4739.7 1627.81  4819.7 1629.17  4829.7 1627.99
  4919.8 1624.39  4929.8 1623.18  4939.8 1620.53  4950.1 1616.74  4959.8 1613.54
  4979.8 1612.03  4984.2 1611.01  4984.7 1610.51  4995.4 1611.01  5052.9 1614.96
  5120.0 1617.10  5164.7 1623.83  5195.8 1625.97  5220.6 1629.26  5237.2 1629.52
  5268.9 1628.25  5297.1 1628.59  5313.3 1625.52  5357.0 1627.50  5394.0 1627.02
  5406.4 1626.11  5416.7 1626.61  5422.6 1628.28  5519.1 1628.87  5661.7 1631.59
#Mann=5,-1,0
  4498.9   0.035       0  4950.1     0.1       0  4984.2    0.05       0
  4995.4     0.1       0  5195.8   0.035       0
Bank Sta=4984.2,4995.4
Exp/Cntr=0.3,0.1

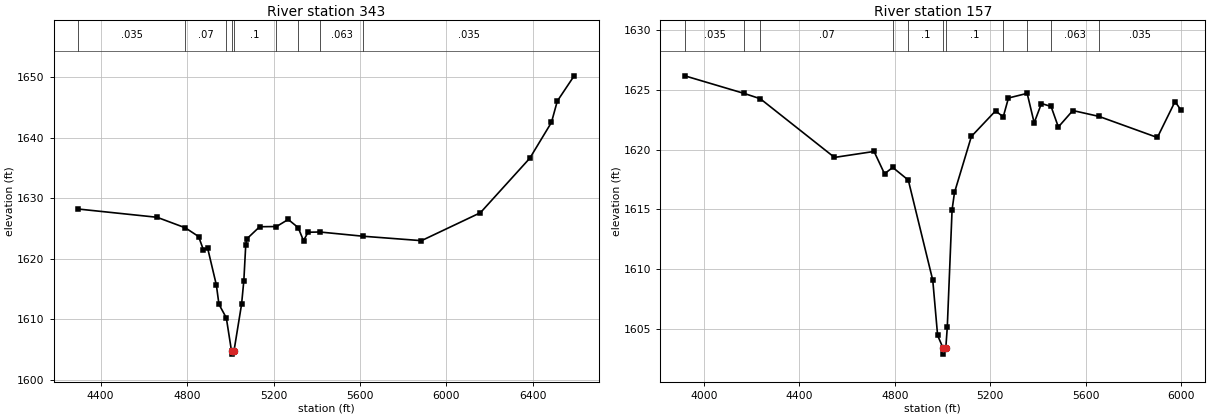
Type RM Length L Ch R = 1,343,186,186,186
BEGIN DESCRIPTION:
Mico Creek 1.0
END DESCRIPTION:
XS GIS Cut Line= 5
      1934156.41     13871148.60      1934526.30     13871552.16
      1934818.41     13871641.99      1935496.76     13871535.09
      1936098.76     13871080.37
#Sta/Elev= 30
  4296.8 1628.20  4661.1 1626.84  4791.9 1625.10  4853.3 1623.66  4875.2 1621.49
  4895.2 1621.73  4935.4 1615.67  4947.5 1612.47  4981.5 1610.24  5005.6 1604.75
  5006.1 1604.25  5016.9 1604.75  5052.1 1612.48  5062.6 1616.38  5071.4 1622.27
  5076.6 1623.28  5135.8 1625.28  5213.6 1625.31  5267.9 1626.48  5313.9 1625.14
  5338.7 1622.98  5359.7 1624.37  5414.1 1624.41  5614.7 1623.71  5884.5 1622.98
  6157.1 1627.59  6385.8 1636.59  6485.9 1642.50  6513.0 1646.02  6591.0 1650.19
#Mann=9,-1,0
  4296.8   0.035       0  4791.9    0.07       0  4981.5     0.1       0
  5005.6    0.05       0  5016.9     0.1       0  5213.6    0.07       0
  5313.9   0.035       0  5414.1   0.063       0  5614.7   0.035       0
Bank Sta=5005.6,5016.9
Exp/Cntr=0.3,0.1

Type RM Length L Ch R = 1,157,0,0,0
BEGIN DESCRIPTION:
Mico Creek 0.0
END DESCRIPTION:
XS GIS Cut Line= 4
      1933587.26     13871476.92      1934377.03     13871729.98
      1934768.96     13871790.40      1935611.33     13871656.01
#Sta/Elev= 30
  3919.9 1626.19  4169.5 1624.71  4236.3 1624.27  4547.5 1619.35  4713.4 1619.85
  4757.3 1617.98  4791.8 1618.51  4857.0 1617.45  4959.6 1609.05  4979.9 1604.43
  5002.9 1603.36  5003.4 1602.86  5014.2 1603.36  5020.4 1605.10  5040.6 1614.97
  5050.7 1616.41  5121.5 1621.11  5222.8 1623.25  5255.1 1622.75  5276.9 1624.33
  5355.4 1624.72  5384.8 1622.25  5415.2 1623.87  5455.7 1623.62  5486.1 1621.90
  5546.8 1623.28  5656.3 1622.79  5901.3 1621.02  5975.3 1624.03  5998.8 1623.36
#Mann=11,-1,0
  3919.9   0.035       0  4169.5     0.1       0  4236.3    0.07       0
  4791.8   0.035       0  4857.0     0.1       0  5002.9    0.05       0
  5014.2     0.1       0  5255.1    0.07       0  5355.4   0.035       0
  5455.7   0.063       0  5656.3   0.035       0
Bank Sta=5002.9,5014.2
Exp/Cntr=0.3,0.1

Chan Stop Cuts=-1