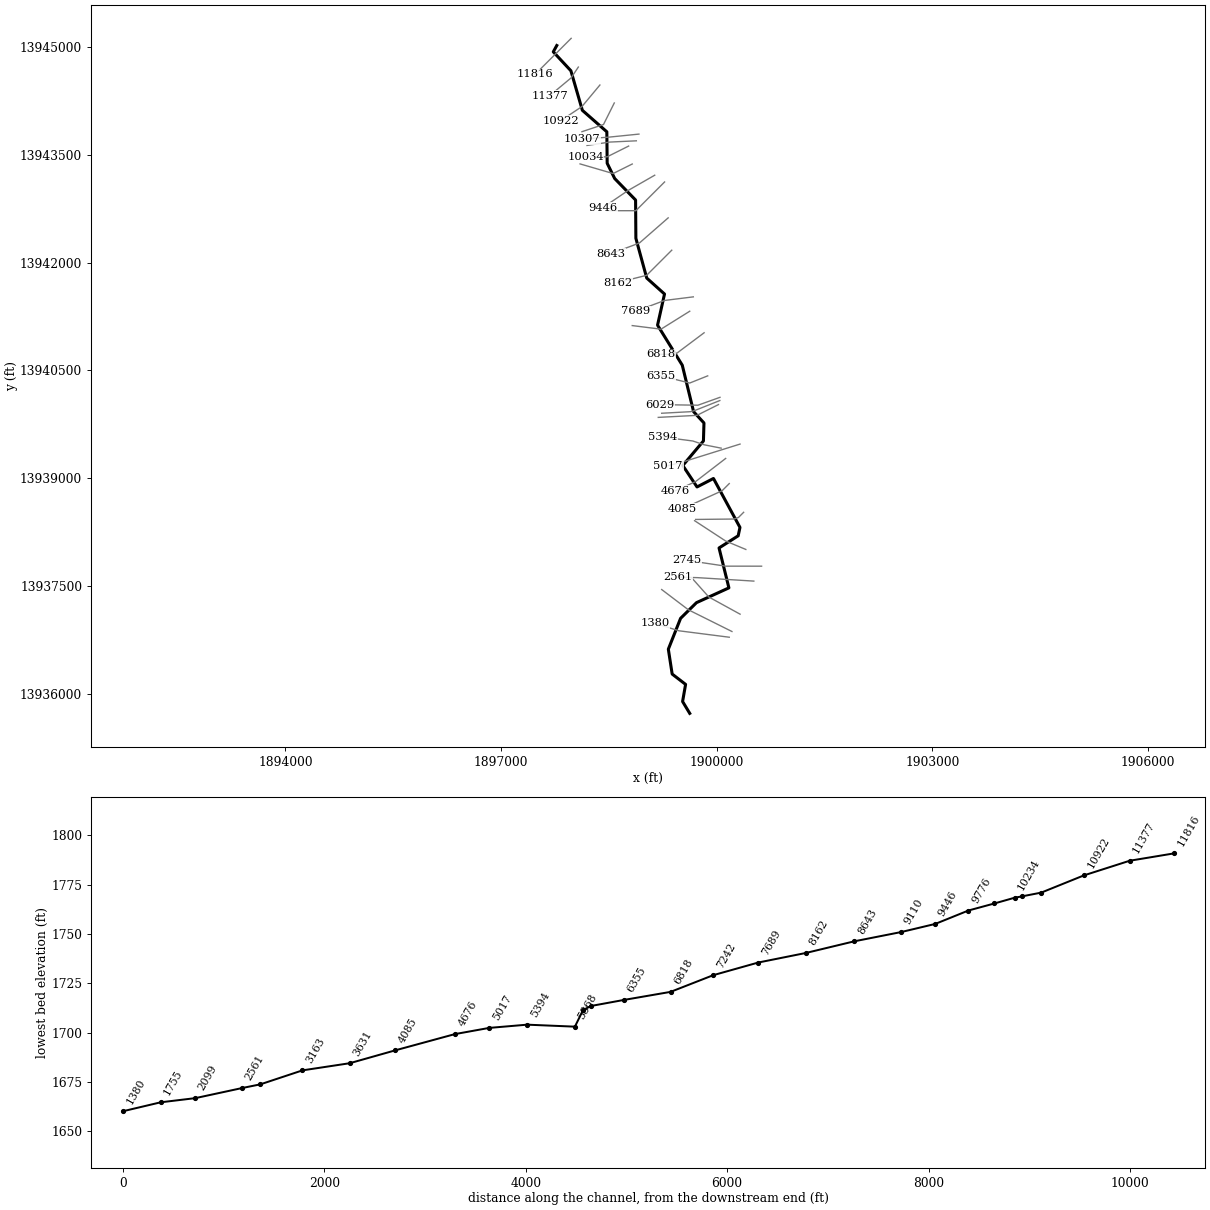
--- Nichols Creek.prj (project) ---

Proj Title=Nichols Creek Base Level Engineering
Current Plan=p01
Default Exp/Contr=0.3,0.1
English Units
Geom File=g01
Flow File=f01
Plan File=p01
Y Axis Title=Elevation
X Axis Title(PF)=Main Channel Distance
X Axis Title(XS)=Station
BEGIN DESCRIPTION:
Nichols Creek
END DESCRIPTION:
DSS Export Rating Curves= 0
DSS Export Rating Curve Sorted= 0
DSS Export Volume Flow Curves= 0
DXF OffsetX= 0
DXF OffsetY= 0
DXF ScaleX= 1
DXF ScaleY= 10

--- Nichols Creek.p01 (plan) ---

Plan Title=Multiple Run
Short Identifier=Multiple
Geom File=g01
Flow File=f01
Subcritical Flow
K Sum by GR= 0
Std Step Tol= 0.01
Critical Tol= 0.01
Num of Std Step Trials= 20
Max Error Tol= 0.3
Flow Tol Ratio= 0.001
Split Flow NTrial= 30
Split Flow Tol= 0.02
Split Flow Ratio= 0.02
Log Output Level= 0
Friction Slope Method= 1
Unsteady Friction Slope Method= 2
Unsteady Bridges Friction Slope Method= 1
Parabolic Critical Depth
Global Vel Dist=  1 , 1 , 1
Global Log Level= 0
CheckData=True
Encroach Param= -1, 0, 0, 0
BEGIN DESCRIPTION:
Multiple Run
END DESCRIPTION:

--- Nichols Creek.f01 (steady flow) ---

Flow Title=Multiple
Program Version=4.10
Number of Profiles= 7
Profile Names=10-year,25-year,50-year,1pct_min,100-year,1pct_plu,500-year
River Rch & RM=Nichols Creek,Reach-1         ,11816
     989    1688    2354    1589    3171    6327    5679
River Rch & RM=Nichols Creek,Reach-1         ,10307
    1272    2205    3106    2116    4223    8426    7709
River Rch & RM=Nichols Creek,Reach-1         ,9446
    2021    3572    5098    3510    7004   13974   13068
Boundary for River Rch & Prof#=Nichols Creek,Reach-1         , 1
Up Type= 0
Dn Type= 3
Dn Slope=0.01
Boundary for River Rch & Prof#=Nichols Creek,Reach-1         , 2
Up Type= 0
Dn Type= 3
Dn Slope=0.01
Boundary for River Rch & Prof#=Nichols Creek,Reach-1         , 3
Up Type= 0
Dn Type= 3
Dn Slope=0.01
Boundary for River Rch & Prof#=Nichols Creek,Reach-1         , 4
Up Type= 0
Dn Type= 3
Dn Slope=0.01
Boundary for River Rch & Prof#=Nichols Creek,Reach-1         , 5
Up Type= 0
Dn Type= 3
Dn Slope=0.01
Boundary for River Rch & Prof#=Nichols Creek,Reach-1         , 6
Up Type= 0
Dn Type= 3
Dn Slope=0.01
Boundary for River Rch & Prof#=Nichols Creek,Reach-1         , 7
Up Type= 0
Dn Type= 3
Dn Slope=0.01
DSS Import GetInterval= 0
DSS Import GetPeak= 0
DSS Import FillOption= 0

--- Nichols Creek.g01 (geometry) ---

Geom Title=Existing Conditions
Program Version=4.10

River Reach=Nichols Creek   ,Reach-1
Reach XY= 30
        1897775.       13945025.      1897726.36     13944936.98
      1897971.26     13944673.48      1898130.83      13944122.7
       1898471.4     13943823.51       1898476.2      13943385.5
      1898580.84      13943172.7      1898871.47     13942873.55
      1898875.52     13942340.22      1899026.64     13941786.83
      1899274.07     13941564.52      1899177.06     13941130.86
      1899521.17     13940573.42      1899678.54     13939926.46
      1899822.95     13939769.14       1899815.7     13939518.33
      1899528.34     13939176.72      1899726.43     13938878.01
      1899955.21     13938996.07      1900323.92     13938314.45
      1900299.04     13938197.67      1900032.79     13938028.42
      1900169.92     13937472.69      1899718.94     13937266.86
      1899497.71     13937048.47      1899327.24     13936619.07
      1899380.52     13936272.56      1899567.31     13936128.67
       1899525.5      13935890.2        1899625.       13935725.

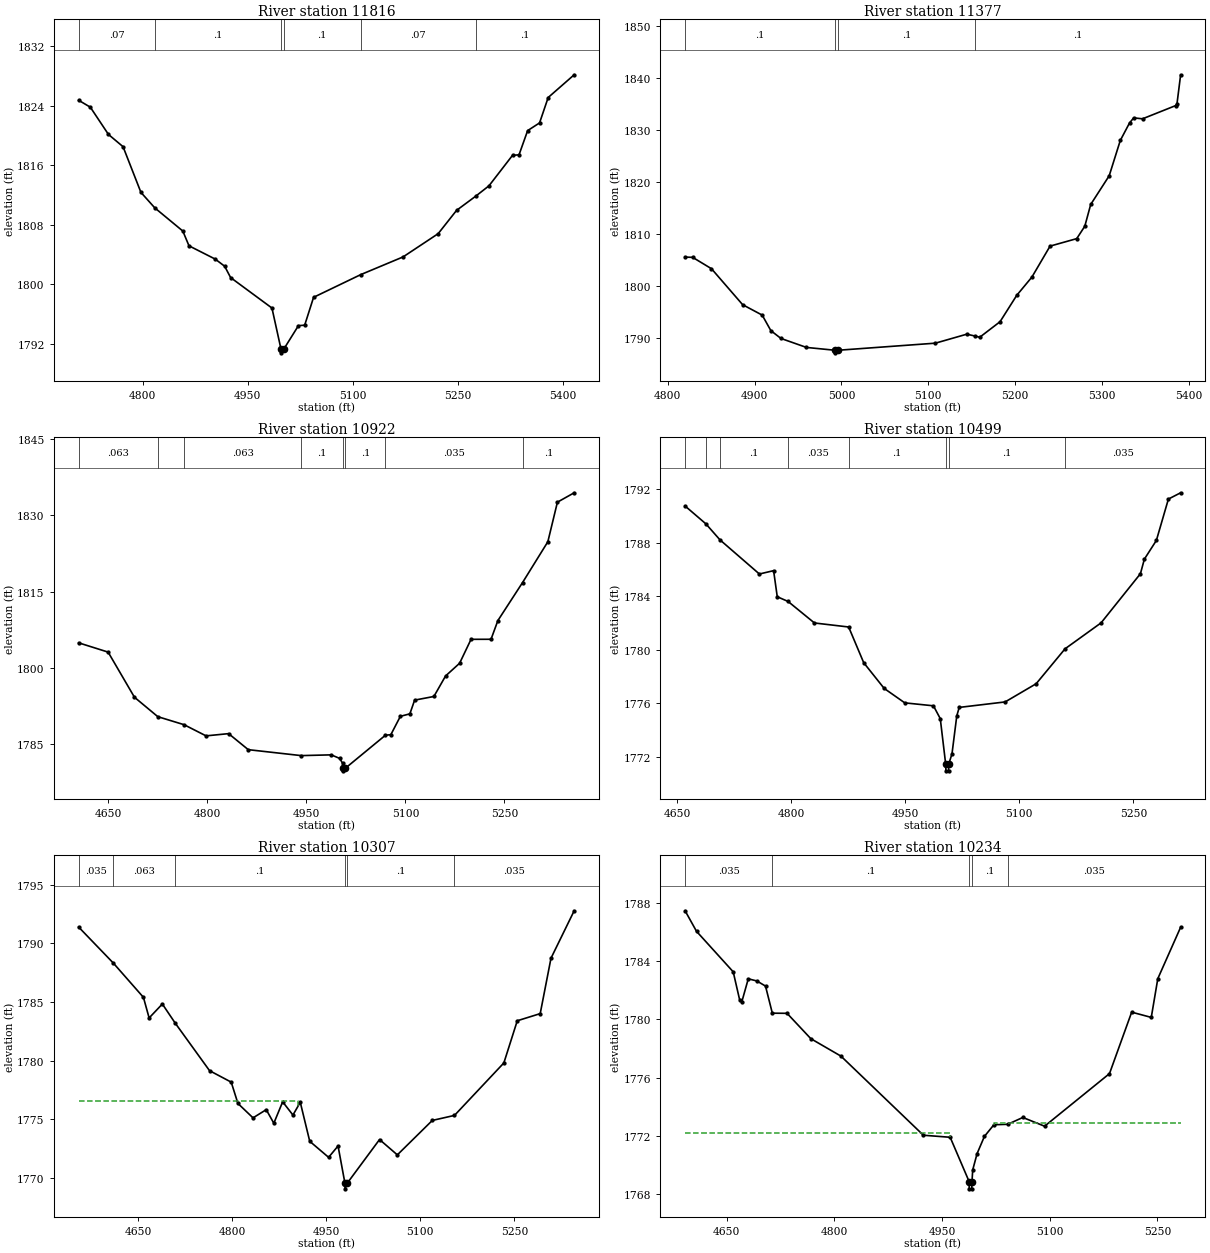
Type RM Length L Ch R = 1 ,11816   ,439,439,439
BEGIN DESCRIPTION:
Nichols Creek 26.0
END DESCRIPTION:
XS GIS Cut Line= 3
      1897975.03     13945125.03        1897775.       13944925.
      1897474.97     13944624.97
#Sta/Elev= 30
  4708.7 1824.72  4725.4 1823.79  4751.3 1820.13  4772.1 1818.49  4797.6 1812.36
  4817.4 1810.28  4857.4 1807.17  4866.2 1805.19  4903.6 1803.41  4917.1 1802.45
  4925.6 1800.93  4984.6 1796.84  4997.5 1791.33  4997.7 1790.83  5001.5 1791.33
  5022.4 1794.48  5031.3 1794.54    5044 1798.28  5111.2 1801.32  5171.7  1803.7
  5221.8 1806.82  5248.1 1809.95  5275.1 1811.83  5294.3 1813.24  5327.9 1817.33
  5337.2  1817.4  5349.5 1820.65  5366.5 1821.68  5378.8 1825.09  5415.9 1828.14
#Mann= 6 ,-1 , 0
  4708.7     .07       0  4817.4      .1       0  4997.5     .05       0
  5001.5      .1       0  5111.2     .07       0  5275.1      .1       0
Bank Sta=4997.5,5001.5
XS Rating Curve= 0 ,0
Exp/Cntr=0.3,0.1

Type RM Length L Ch R = 1 ,11377   ,455,455,455
BEGIN DESCRIPTION:
Nichols Creek 25.0
END DESCRIPTION:
XS GIS Cut Line= 3
      1898074.99     13944724.98        1897975.       13944575.
      1897674.98     13944324.98
#Sta/Elev= 30
  4819.9 1805.53  4828.6 1805.48  4850.3 1803.29  4886.2 1796.37  4908.7 1794.37
  4918.7 1791.38  4930.3 1789.88  4959.7 1788.15  4992.4 1787.61  4992.6 1787.11
  4996.4 1787.61  5108.2 1788.97  5144.4  1790.7  5154.3 1790.32  5159.3 1790.11
  5182.7  1793.1  5201.9 1798.17  5219.4 1801.69  5240.3 1807.64    5271 1809.08
  5280.3 1811.46  5287.1 1815.65  5308.4 1821.17  5321.2 1827.97  5331.8 1831.32
  5336.6 1832.31  5346.8 1832.13  5385.1 1834.68  5386.5 1835.03  5390.7  1840.6
#Mann= 4 ,-1 , 0
  4819.9      .1       0  4992.4    .035       0  4996.4      .1       0
  5154.3      .1       0
Bank Sta=4992.4,4996.4
XS Rating Curve= 0 ,0
Exp/Cntr=0.3,0.1

Type RM Length L Ch R = 1 ,10922   ,423,423,423
BEGIN DESCRIPTION:
Nichols Creek 24.0
END DESCRIPTION:
XS GIS Cut Line= 3
      1898374.98     13944474.98        1898125.       13944175.
      1897825.03     13943975.02
#Sta/Elev= 30
  4604.8  1804.9  4649.5 1803.07  4689.4 1794.18  4724.8 1790.35  4764.6 1788.77
  4797.9 1786.57  4832.1 1787.01  4861.9 1783.85  4942.1 1782.68  4987.6 1782.83
  5000.4 1782.13  5004.8 1781.18  5004.9 1780.18  5005.2 1779.68  5008.9 1780.18
  5069.7 1786.69    5078 1786.81  5092.4 1790.42  5106.8 1790.91    5114 1793.61
  5143.2 1794.33  5160.9 1798.37  5182.2 1800.88  5199.5 1805.59  5229.8  1805.6
  5240.2 1809.29  5277.5 1816.76  5315.9 1824.81  5330.4 1832.61  5355.8 1834.46
#Mann= 8 ,-1 , 0
  4604.8    .063       0  4724.8    .035       0  4764.6    .063       0
  4942.1      .1       0  5004.9     .05       0  5008.9      .1       0
  5069.7    .035       0  5277.5      .1       0
Bank Sta=5004.9,5008.9
XS Rating Curve= 0 ,0
Exp/Cntr=0.3,0.1

Type RM Length L Ch R = 1 ,10499   ,192,192,192
BEGIN DESCRIPTION:
Nichols Creek 23.0
END DESCRIPTION:
XS GIS Cut Line= 3
      1898575.01     13944225.01        1898425.       13943925.
      1898124.95     13943824.98
#Sta/Elev= 30
  4660.5 1790.75  4687.8 1789.42  4706.4 1788.22  4758.2 1785.67  4776.9 1785.92
  4781.7 1783.97  4795.9 1783.62  4830.6 1782.01  4875.6 1781.71  4895.4 1779.04
  4922.3 1777.12  4949.4 1776.04  4987.1 1775.82  4996.1 1774.86  5003.2 1771.46
  5003.5 1770.96    5007 1770.96  5007.2 1771.46  5011.5 1772.23  5017.8 1775.07
    5021  1775.7  5081.4 1776.11  5122.2 1777.47  5160.2 1780.08  5207.6 1782.02
  5259.3 1785.69  5264.5 1786.78  5280.3 1788.18  5296.1 1791.27  5312.2 1791.74
#Mann= 8 ,-1 , 0
  4660.5    .063       0  4687.8    .035       0  4706.4      .1       0
  4795.9    .035       0  4875.6      .1       0  5003.2     .05       0
  5007.2      .1       0  5160.2    .035       0
Bank Sta=5003.2,5007.2
XS Rating Curve= 0 ,0
Exp/Cntr=0.3,0.1

Type RM Length L Ch R = 1 ,10307   ,73,73,73
BEGIN DESCRIPTION:
Nichols Creek 22.1
END DESCRIPTION:
XS GIS Cut Line= 3
      1898918.09      13943791.5      1898493.62     13943748.53
       1898130.3     13943723.79
#Sta/Elev= 30
  4554.7  1791.4    4610 1788.33  4658.1  1785.4  4667.2 1783.64  4688.3 1784.83
  4708.8  1783.2  4763.6 1779.14  4798.2 1778.16  4808.9 1776.34    4833 1775.11
  4854.1 1775.81  4866.2 1774.65  4880.3 1776.48  4896.7 1775.35  4908.4 1776.44
  4923.5 1773.11  4953.6 1771.74  4968.7 1772.71  4979.6 1769.55  4979.9 1769.05
  4983.6 1769.55  5034.9 1773.26  5063.3 1771.95  5119.1 1774.89  5154.5 1775.32
  5233.3  1779.8  5254.7  1783.4  5291.3 1784.01  5308.5 1788.74  5345.5 1792.79
#Mann= 6 ,-1 , 0
  4554.7    .035       0    4610    .063       0  4708.8      .1       0
  4979.6     .05       0  4983.6      .1       0  5154.5    .035       0
#XS Ineff= 2 , 0
          4904.5 1776.56
Permanent Ineff=
       F       F
Bank Sta=4979.6,4983.6
XS Rating Curve= 0 ,0
Exp/Cntr=0.3,0.1

Type RM Length L Ch R = 1 ,10234   ,200,200,200
BEGIN DESCRIPTION:
Mapping XS 20a846aa
END DESCRIPTION:
XS GIS Cut Line= 3
      1898882.08     13943697.93      1898511.53     13943680.48
      1898195.78      13943633.4
#Sta/Elev= 30
  4592.1 1787.45    4608 1786.04  4659.1 1783.26  4668.1 1781.33  4671.1  1781.2
  4680.1 1782.78  4692.1 1782.63  4704.1 1782.28  4713.6 1780.42  4734.1 1780.41
  4767.2 1778.67  4809.2 1777.47    4924 1772.04  4961.3  1771.9  4987.7 1768.86
  4987.9 1768.36  4991.4 1768.36  4991.7 1768.86  4992.7 1769.66  4998.8 1770.78
    5009 1771.96  5022.2 1772.76  5041.4 1772.79  5062.5 1773.26  5092.8 1772.66
  5183.2 1776.27  5214.1 1780.49  5241.4 1780.13  5250.5 1782.79  5282.3 1786.32
#Mann= 5 ,-1 , 0
  4592.1    .035       0  4713.6      .1       0  4987.7     .05       0
  4991.7      .1       0  5041.4    .035       0
#XS Ineff= 2 , 0
         4961.14 1772.19 5021.88         1772.88
Permanent Ineff=
       F       F
Bank Sta=4987.7,4991.7
XS Rating Curve= 0 ,0
Exp/Cntr=0.3,0.1

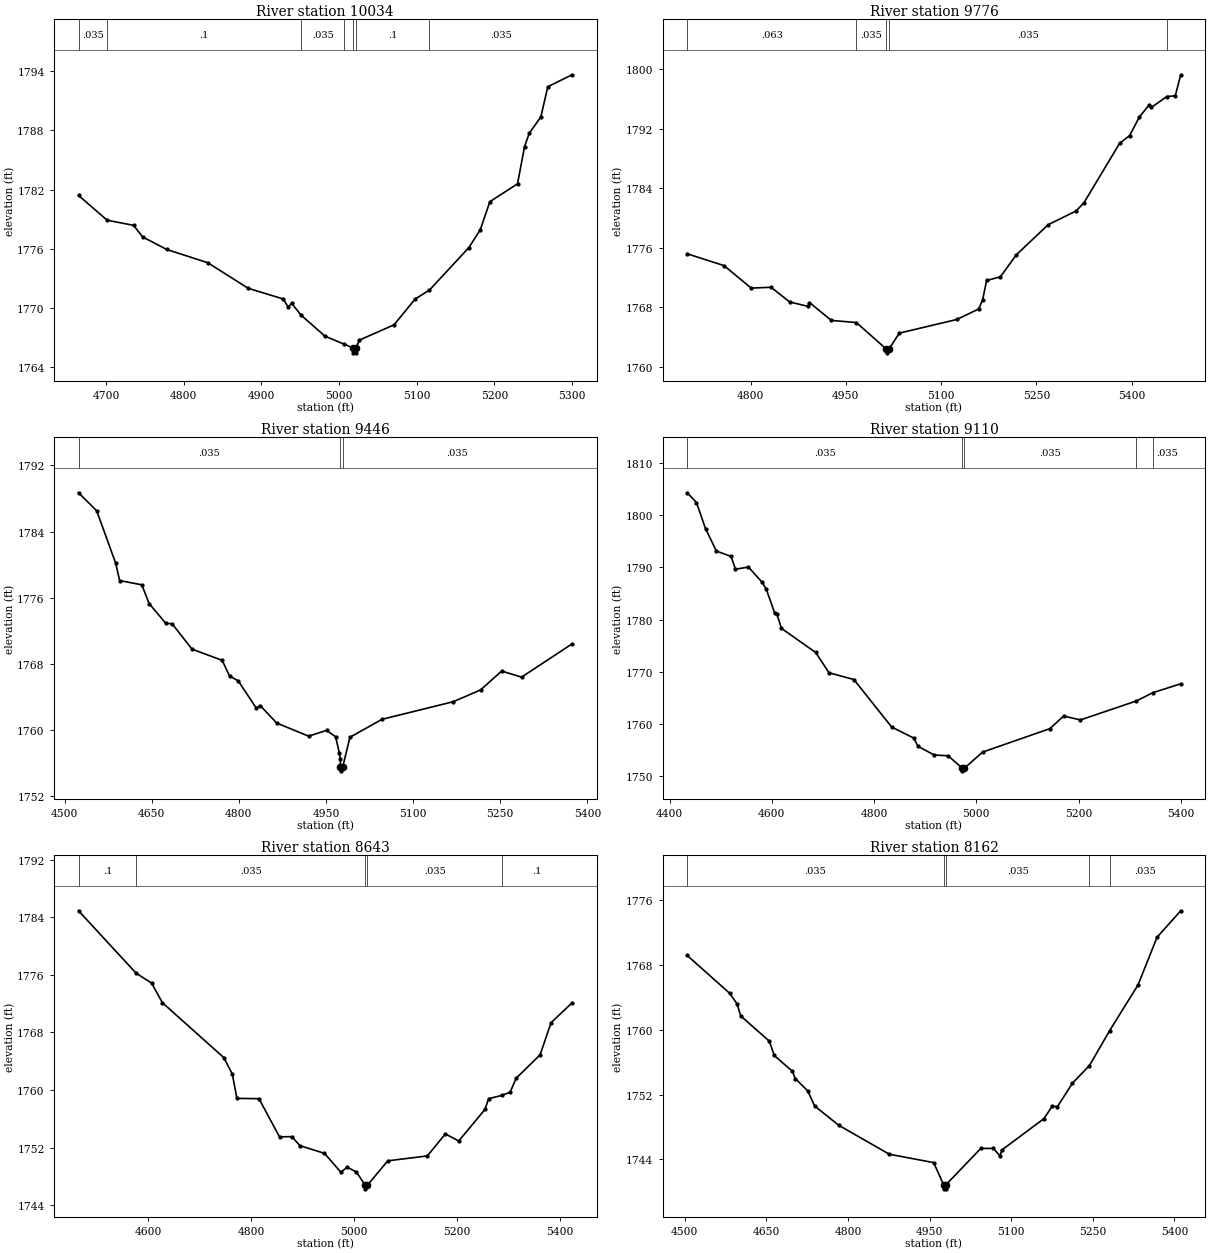
Type RM Length L Ch R = 1 ,10034   ,258,258,258
BEGIN DESCRIPTION:
Nichols Creek 22.0
END DESCRIPTION:
XS GIS Cut Line= 3
        1898775.       13943625.        1898475.       13943475.
      1898175.01       13943475.
#Sta/Elev= 30
  4664.5 1781.41  4701.4  1778.9  4735.4 1778.38    4747 1777.21  4777.9 1775.94
  4830.9 1774.59    4883    1772  4928.1 1770.92  4934.4  1770.1  4938.9 1770.48
    4951 1769.28  4981.8 1767.15  5006.8 1766.33  5017.7 1765.96    5018 1765.46
  5021.5 1765.46  5021.7 1765.96  5026.1 1766.75  5070.7  1768.3  5097.7  1770.9
  5116.3 1771.82  5167.1 1776.13  5181.7 1777.93  5194.1 1780.78  5229.7 1782.59
  5238.7 1786.35  5244.7  1787.7  5259.7 1789.37  5268.7 1792.43  5299.9 1793.64
#Mann= 7 ,-1 , 0
  4664.5    .035       0  4701.4      .1       0    4951    .035       0
  5006.8      .1       0  5017.7    .035       0  5021.7      .1       0
  5116.3    .035       0
Bank Sta=5017.7,5021.7
XS Rating Curve= 0 ,0
Exp/Cntr=0.3,0.1

Type RM Length L Ch R = 1 ,9776    ,330,330,330
BEGIN DESCRIPTION:
Nichols Creek 21.0
END DESCRIPTION:
XS GIS Cut Line= 3
      1898824.96     13943374.98      1898559.07     13943242.11
       1898098.9     13943376.38
#Sta/Elev= 30
  4700.4  1775.2  4758.3 1773.61  4801.1 1770.59  4832.4  1770.7  4861.5 1768.73
  4890.6 1768.13  4892.8 1768.65  4927.1 1766.25  4966.6 1765.96  5013.8 1762.39
  5014.1 1761.89  5017.8 1762.39  5034.2 1764.54  5124.6 1766.37    5159 1767.78
  5165.2 1768.99  5171.5 1771.61  5193.3 1772.11  5218.3 1775.06  5268.3  1779.1
  5312.1 1780.94  5324.6 1782.04  5380.9 1790.05  5396.5 1791.07  5412.1  1793.6
  5427.7 1795.24  5430.9 1794.87  5455.2 1796.33  5468.4 1796.43    5477 1799.25
#Mann= 5 ,-1 , 0
  4700.4    .063       0  4966.6    .035       0  5013.8    .035       0
  5017.8    .035       0  5455.2      .1       0
Bank Sta=5013.8,5017.8
XS Rating Curve= 0 ,0
Exp/Cntr=0.3,0.1

Type RM Length L Ch R = 1 ,9446    ,336,336,336
BEGIN DESCRIPTION:
Mapping XS d5d7660b
END DESCRIPTION:
XS GIS Cut Line= 3
      1899137.66      13943218.9      1898768.04      13943006.8
      1898418.06     13942768.78
#Sta/Elev= 30
  4524.1 1788.68  4555.4  1786.5    4588 1780.17  4594.9 1778.07    4633 1777.56
  4645.5  1775.3  4674.5 1772.89  4685.1 1772.86  4719.5 1769.78  4771.4 1768.43
    4784 1766.54    4799 1765.95    4830 1762.66  4836.7 1762.97  4865.3 1760.85
  4920.1 1759.27    4951 1759.97  4966.5  1759.2    4973 1757.24  4974.7 1756.46
  4974.9 1755.58  4975.1 1755.08  4978.9 1755.58  4991.2 1759.14  5046.6 1761.31
  5168.9 1763.43  5216.1 1764.86  5252.4 1767.14  5286.6  1766.4  5373.5 1770.42
#Mann= 3 ,-1 , 0
  4524.1    .035       0  4974.9    .035       0  4978.9    .035       0
Bank Sta=4974.9,4978.9
XS Rating Curve= 0 ,0
Exp/Cntr=0.3,0.1

Type RM Length L Ch R = 1 ,9110    ,467,467,467
BEGIN DESCRIPTION:
Nichols Creek 20.0
END DESCRIPTION:
XS GIS Cut Line= 3
      1899274.97     13943124.97        1898875.       13942725.
      1898475.05       13942725.
#Sta/Elev= 30
  4434.4 1804.32  4452.5 1802.45  4470.2 1797.46  4491.4 1793.15  4520.3  1792.1
  4528.8 1789.66  4554.3 1790.07  4580.5  1787.2    4589 1785.86  4605.2 1781.34
  4609.8  1781.1  4618.7 1778.32  4685.8 1773.69  4711.7 1769.81  4760.5  1768.5
  4834.3  1759.4  4877.5 1757.28    4886 1755.69  4917.4 1754.04    4945 1753.87
  4972.7 1751.49    4973 1750.99  4976.7 1751.49  5012.2 1754.58  5144.2 1759.09
  5170.8  1761.5  5203.8 1760.75  5313.4  1764.4  5345.4 1765.98    5400 1767.68
#Mann= 5 ,-1 , 0
  4434.4    .035       0  4972.7    .035       0  4976.7    .035       0
  5313.4      .1       0  5345.4    .035       0
Bank Sta=4972.7,4976.7
XS Rating Curve= 0 ,0
Exp/Cntr=0.3,0.1

Type RM Length L Ch R = 1 ,8643    ,481,481,481
BEGIN DESCRIPTION:
Nichols Creek 19.0
END DESCRIPTION:
XS GIS Cut Line= 3
      1899324.98     13942624.99        1898925.       13942275.
      1898524.99       13942125.
#Sta/Elev= 30
  4464.4 1784.89  4576.3 1776.22  4606.2 1774.86  4627.4 1772.12  4746.5 1764.51
  4763.1 1762.22  4772.1 1758.84  4814.9  1758.8  4854.8  1753.5  4878.7 1753.53
  4894.6 1752.27  4942.1 1751.21    4974 1748.59  4986.3 1749.29  5004.2 1748.61
  5021.4 1746.78  5021.6 1746.28  5025.5 1746.78  5065.1 1750.17    5142 1750.85
    5177 1753.91  5202.9 1752.92  5254.1 1757.32  5260.9  1758.8  5286.5 1759.25
  5302.8  1759.7  5314.5 1761.63  5361.1  1764.9  5382.3 1769.35  5423.1 1772.11
#Mann= 5 ,-1 , 0
  4464.4      .1       0  4576.3    .035       0  5021.4    .035       0
  5025.5    .035       0  5286.5      .1       0
Bank Sta=5021.4,5025.5
XS Rating Curve= 0 ,0
Exp/Cntr=0.3,0.1

Type RM Length L Ch R = 1 ,8162    ,473,473,473
BEGIN DESCRIPTION:
Nichols Creek 18.0
END DESCRIPTION:
XS GIS Cut Line= 3
      1899375.01     13942175.01        1899025.       13941825.
      1898625.01       13941725.
#Sta/Elev= 30
  4504.5 1769.19  4582.9  1764.5  4596.2  1763.2  4602.9 1761.72  4655.6  1758.6
  4664.4 1756.84    4698 1754.89    4703 1753.99    4726 1752.48  4738.7 1750.61
  4782.8 1748.23  4876.2 1744.64  4957.6 1743.61  4975.9 1740.87  4976.2 1740.37
  4979.8 1740.37  4980.1 1740.87  5044.2 1745.36  5067.3 1745.36  5079.7 1744.42
  5082.8 1745.16  5160.1 1749.03  5175.6 1750.57  5185.2 1750.53  5212.7 1753.42
    5244  1755.6  5281.2 1759.92  5333.3 1765.55  5368.2 1771.44  5411.8 1774.71
#Mann= 5 ,-1 , 0
  4504.5    .035       0  4975.9    .035       0  4980.1    .035       0
    5244      .1       0  5281.2    .035       0
Bank Sta=4975.9,4980.1
XS Rating Curve= 0 ,0
Exp/Cntr=0.3,0.1

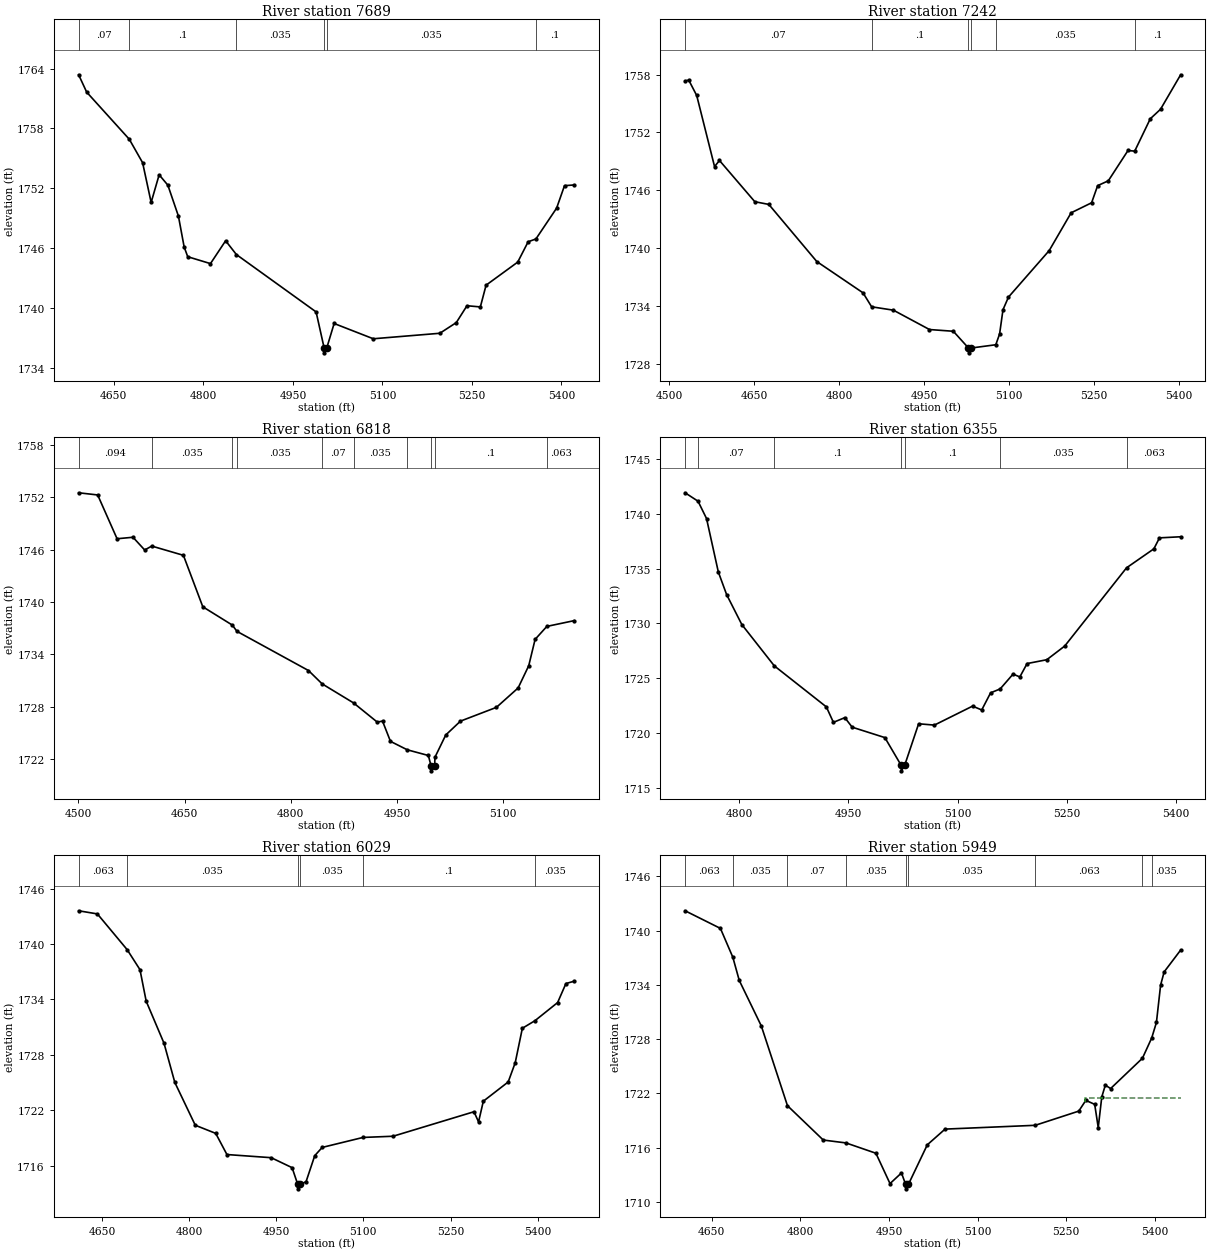
Type RM Length L Ch R = 1 ,7689    ,447,447,447
BEGIN DESCRIPTION:
Nichols Creek 17.0
END DESCRIPTION:
XS GIS Cut Line= 3
        1899675.       13941525.        1899275.       13941475.
      1898875.01       13941325.
#Sta/Elev= 30
    4591 1763.38  4604.5 1761.64  4675.9 1756.92  4698.2 1754.57  4712.5 1750.59
  4725.9 1753.36  4740.5 1752.32  4758.2 1749.22  4767.8 1746.13  4773.8 1745.15
  4811.9 1744.46  4837.3 1746.75  4855.3 1745.37  4988.9 1739.62  5002.3 1736.02
  5002.7 1735.52  5006.8 1736.02  5019.1 1738.46  5084.7 1736.93  5196.2 1737.48
  5223.8 1738.55  5241.7 1740.24  5264.1 1740.12  5273.7  1742.3  5326.7 1744.61
  5344.2 1746.65  5357.2 1746.93  5391.9 1750.02  5405.1 1752.27  5421.3 1752.34
#Mann= 6 ,-1 , 0
    4591     .07       0  4675.9      .1       0  4855.3    .035       0
  5002.3    .035       0  5006.8    .035       0  5357.2      .1       0
Bank Sta=5002.3,5006.8
XS Rating Curve= 0 ,0
Exp/Cntr=0.3,0.1

Type RM Length L Ch R = 1 ,7242    ,424,424,424
BEGIN DESCRIPTION:
Nichols Creek 16.0
END DESCRIPTION:
XS GIS Cut Line= 3
      1899625.01       13941325.        1899225.       13941075.
      1898825.02       13941125.
#Sta/Elev= 30
  4528.3 1757.33  4534.7 1757.43  4548.8 1755.83  4580.3 1748.45    4589 1749.08
  4651.4  1744.8  4676.1 1744.52  4760.8 1738.59  4842.4 1735.34  4857.6 1733.89
    4896 1733.54  4959.7 1731.53  5001.8 1731.35  5028.6 1729.61  5028.9 1729.11
  5033.2 1729.61  5076.8 1729.95  5083.5 1731.07  5089.5 1733.59  5099.2  1734.9
  5171.1 1739.73  5209.8 1743.65  5245.9 1744.69  5256.6 1746.47  5275.4 1746.97
  5310.2 1750.12    5322 1750.05  5349.5 1753.41  5367.6  1754.4  5403.1 1757.98
#Mann= 6 ,-1 , 0
  4528.3     .07       0  4857.6      .1       0  5028.6     .05       0
  5033.2      .1       0  5076.8    .035       0    5322      .1       0
Bank Sta=5028.6,5033.2
XS Rating Curve= 0 ,0
Exp/Cntr=0.3,0.1

Type RM Length L Ch R = 1 ,6818    ,463,463,463
BEGIN DESCRIPTION:
Nichols Creek 15.0
END DESCRIPTION:
XS GIS Cut Line= 3
      1899825.02     13941025.02        1899425.       13940725.
      1899225.03       13940725.
#Sta/Elev= 30
  4500.2 1752.52  4527.1 1752.27  4554.5 1747.25    4577 1747.42  4593.5 1745.96
  4603.5 1746.41  4648.2 1745.35  4675.6 1739.45  4717.3 1737.35  4723.9 1736.63
  4824.9 1732.14  4844.2 1730.61  4888.5 1728.43    4922 1726.23  4929.5 1726.34
  4940.7 1724.02  4964.5 1723.05  4994.2  1722.4  4998.3 1721.14  4998.6 1720.64
    5003 1721.14  5003.6 1722.21  5018.8 1724.75  5039.6 1726.34  5090.4 1727.92
    5121 1730.14    5136 1732.69    5145 1735.71  5161.6  1737.2  5200.2 1737.86
#Mann= 10 ,-1 , 0
  4500.2    .094       0  4603.5    .035       0  4717.3     .07       0
  4723.9    .035       0  4844.2     .07       0  4888.5    .035       0
  4964.5      .1       0  4998.3     .05       0    5003      .1       0
  5161.6    .063       0
Bank Sta=4998.3,5003
XS Rating Curve= 0 ,0
Exp/Cntr=0.3,0.1

Type RM Length L Ch R = 1 ,6355    ,326,326,326
BEGIN DESCRIPTION:
Nichols Creek 14.0
END DESCRIPTION:
XS GIS Cut Line= 3
      1899875.01       13940425.        1899625.       13940325.
      1899224.98     13940425.01
#Sta/Elev= 30
  4725.3 1741.91  4743.1 1741.14  4754.8 1739.56    4771 1734.69  4782.4 1732.63
  4803.3  1729.9    4848 1726.13  4919.6 1722.39  4929.3 1720.98    4945 1721.41
  4955.1 1720.54  5000.1 1719.59  5022.5 1717.06  5022.8 1716.56  5027.3 1717.06
  5046.5 1720.85  5068.2 1720.73  5120.7 1722.46  5133.3 1722.11  5145.5 1723.67
  5158.7 1724.03  5176.4 1725.38  5185.7 1725.12  5195.7 1726.34  5222.8 1726.69
  5247.5 1727.94  5332.5 1735.07  5370.1  1736.8  5377.8  1737.8  5406.9  1737.9
#Mann= 7 ,-1 , 0
  4725.3    .063       0  4743.1     .07       0    4848      .1       0
  5022.5     .05       0  5027.3      .1       0  5158.7    .035       0
  5332.5    .063       0
Bank Sta=5022.5,5027.3
XS Rating Curve= 0 ,0
Exp/Cntr=0.3,0.1

Type RM Length L Ch R = 1 ,6029    ,80,80,80
BEGIN DESCRIPTION:
Mapping XS fd2f65c1
END DESCRIPTION:
XS GIS Cut Line= 3
      1900046.02      13940126.1      1899738.76     13940016.19
      1899212.05     13940024.41
#Sta/Elev= 30
  4609.8 1743.59  4642.1 1743.25  4693.4 1739.38  4715.4 1737.22  4726.1 1733.81
  4756.8 1729.26  4775.4 1725.02  4810.6 1720.39  4845.8 1719.51  4865.1 1717.22
  4941.3 1716.88  4977.3  1715.8  4986.9 1714.01  4987.2 1713.51  4991.7 1714.01
  5001.3 1714.28  5016.3  1717.1  5029.1 1717.99  5099.4 1719.07  5151.1  1719.2
  5290.4 1721.85  5298.3 1720.75  5306.5 1722.99  5349.3 1725.07  5361.4 1727.15
  5373.7 1730.88  5395.4  1731.7  5434.4 1733.66  5448.7 1735.72  5462.9 1735.97
#Mann= 6 ,-1 , 0
  4609.8    .063       0  4693.4    .035       0  4986.9    .035       0
  4991.7    .035       0  5099.4      .1       0  5395.4    .035       0
Bank Sta=4986.9,4991.7
XS Rating Curve= 0 ,0
Exp/Cntr=0.3,0.1

Type RM Length L Ch R = 1 ,5949    ,81,81,81
BEGIN DESCRIPTION:
Nichols Creek 13.1
END DESCRIPTION:
XS GIS Cut Line= 4
      1900043.83     13940081.22      1899700.96      13939944.5
      1899635.85     13939926.06      1899234.33     13939904.35
#Sta/Elev= 30
  4604.7  1742.2  4664.5 1740.25  4685.5 1737.06  4696.4 1734.49  4733.7 1729.46
    4778 1720.63  4838.6 1716.83  4877.1 1716.51  4927.7 1715.37  4951.6 1712.01
    4971 1713.19    4978 1711.93  4978.4 1711.43  4982.8 1711.93  5014.7  1716.3
  5044.8 1718.04  5197.4 1718.46  5271.1 1720.03  5283.1 1721.22  5298.1 1720.78
  5304.1 1718.21  5310.1  1721.6  5316.1  1722.9  5325.1 1722.53  5378.9 1725.88
  5394.6 1728.12  5402.6 1729.84  5409.7 1733.98  5415.7 1735.44  5443.6 1737.85
#Mann= 9 ,-1 , 0
  4604.7    .063       0  4685.5    .035       0    4778     .07       0
  4877.1    .035       0    4978    .035       0  4982.8    .035       0
  5197.4    .063       0  5378.9      .1       0  5394.6    .035       0
#XS Ineff= 2 , 0
                         5281.32         1721.53
Permanent Ineff=
       F       F
Bank Sta=4978,4982.8
XS Rating Curve= 0 ,0
Exp/Cntr=0.3,0.1

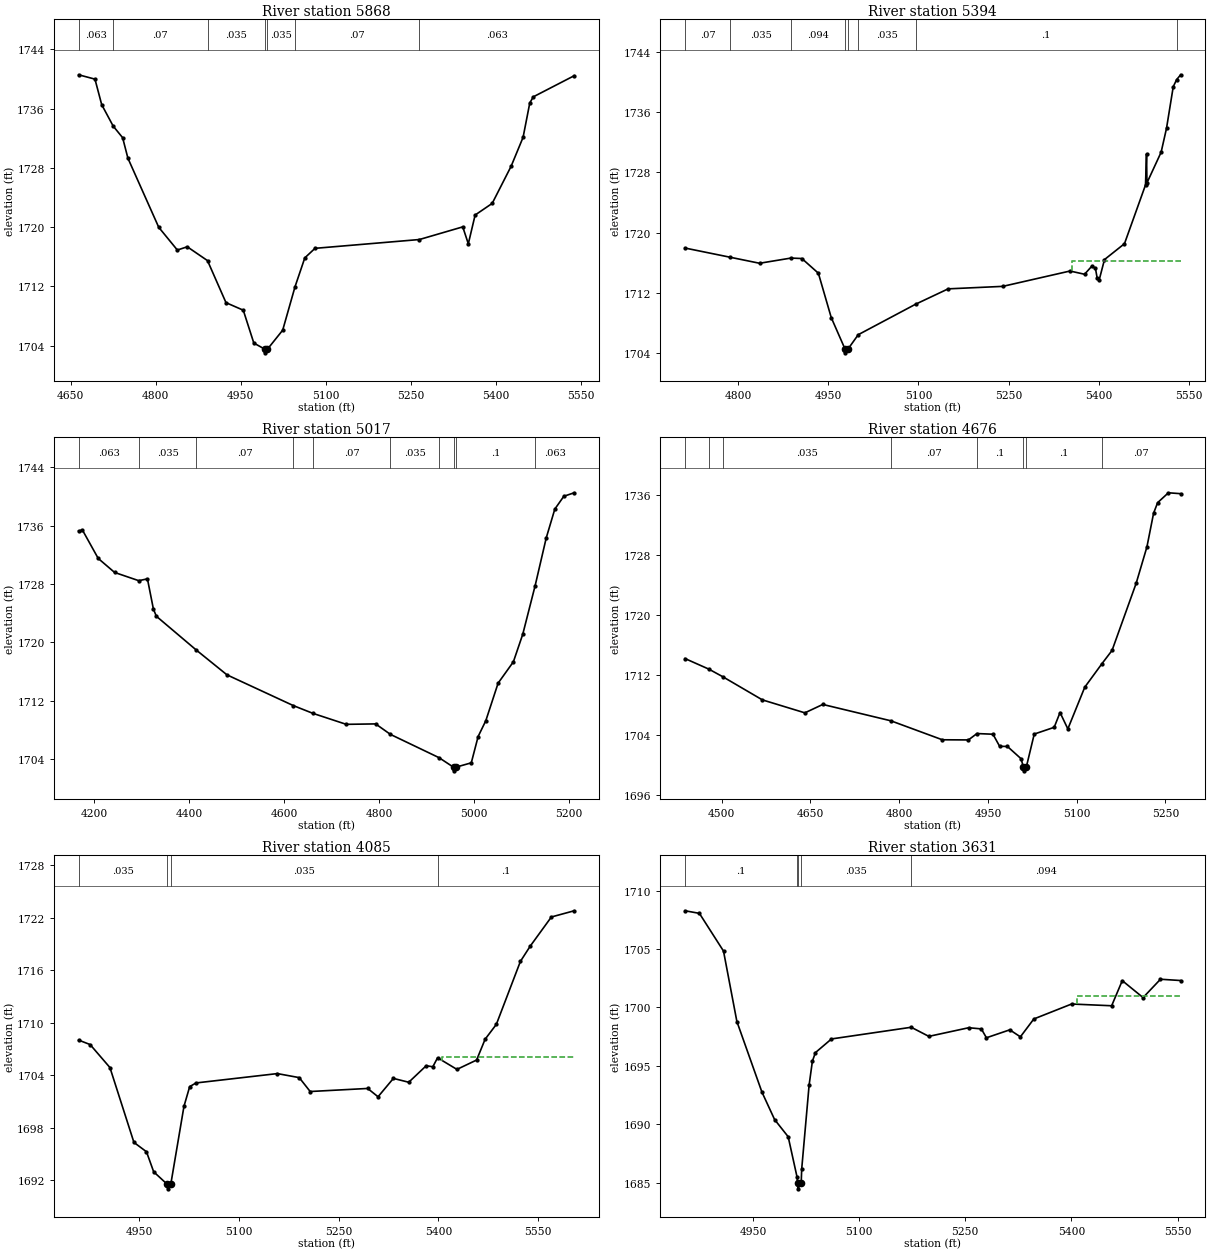
Type RM Length L Ch R = 1 ,5868    ,474,474,474
BEGIN DESCRIPTION:
Nichols Creek 13.0
END DESCRIPTION:
XS GIS Cut Line= 3
      1900025.02     13940025.01        1899725.       13939875.
      1899187.18     13939846.65
#Sta/Elev= 30
  4664.2 1740.58    4693 1739.99  4704.9 1736.54  4725.1 1733.65  4741.8 1732.08
  4751.1 1729.31  4805.5 1719.97  4838.3  1716.9  4855.8 1717.34  4891.5 1715.47
  4924.1 1709.79  4954.6 1708.77  4973.2 1704.33  4992.5 1703.51  4992.8 1703.01
  4997.3 1703.51  5024.1 1706.07  5045.9 1711.95  5063.1 1715.84  5081.1 1717.13
  5265.2 1718.32  5341.7 1720.03  5351.5 1717.74  5363.5 1721.63  5393.6  1723.2
    5427 1728.22  5448.1 1732.13  5459.9 1736.77  5466.1  1737.6  5538.2 1740.45
#Mann= 7 ,-1 , 0
  4664.2    .063       0  4725.1     .07       0  4891.5    .035       0
  4992.5    .035       0  4997.3    .035       0  5045.9     .07       0
  5265.2    .063       0
Bank Sta=4992.5,4997.3
XS Rating Curve= 0 ,0
Exp/Cntr=0.3,0.1

Type RM Length L Ch R = 1 ,5394    ,377,377,377
BEGIN DESCRIPTION:
Nichols Creek 12
END DESCRIPTION:
XS GIS Cut Line= 4
      1900062.28     13939418.25      1899826.82      13939464.9
      1899667.32     13939518.07      1899253.93     13939572.32
#Sta/Elev= 30
  4711.5 1717.94  4786.5 1716.72  4835.5 1715.92  4887.7 1716.61  4905.9 1716.55
  4933.4  1714.6  4954.9 1708.69  4977.8 1704.52  4978.1 1704.02  4982.7 1704.52
  4999.8 1706.43  5095.3 1710.48  5149.5 1712.52  5240.4 1712.85  5352.4 1714.89
  5376.6 1714.46  5388.7 1715.53  5394.7 1715.27  5397.7 1713.91  5400.8 1713.65
  5409.8 1716.41  5443.1 1718.52  5478.1 1726.32  5479.8 1730.43  5480.5  1726.6
  5504.1 1730.67  5513.1 1733.86  5524.3 1739.38  5529.9 1740.31  5536.6 1740.96
#Mann= 8 ,-1 , 0
  4711.5     .07       0  4786.5    .035       0  4887.7    .094       0
  4977.8    .035       0  4982.7    .094       0  4999.8    .035       0
  5095.3      .1       0  5529.9    .035       0
#XS Ineff= 2 , 0
                         5355.24         1716.17
Permanent Ineff=
       F       F
Bank Sta=4977.8,4982.7
XS Rating Curve= 0 ,0
Exp/Cntr=0.3,0.1

Type RM Length L Ch R = 1 ,5017    ,341,341,341
BEGIN DESCRIPTION:
Nichols Creek 11.0
END DESCRIPTION:
XS GIS Cut Line= 3
        1900325.       13939475.        1899525.       13939225.
      1899325.01       13939175.
#Sta/Elev= 30
  4167.1 1735.28    4175 1735.43  4208.4 1731.52  4242.9  1729.6  4293.8 1728.47
  4312.1 1728.72  4324.7 1724.57  4330.9 1723.59  4415.1 1718.95  4479.7 1715.55
  4619.6 1711.33  4661.1 1710.26  4731.1 1708.76    4793 1708.82  4824.2 1707.38
  4926.5 1704.19  4957.1 1702.88  4957.5 1702.38  4962.1 1702.88  4994.6 1703.48
    5009 1707.09  5025.2 1709.26  5051.1 1714.41  5083.3 1717.34  5103.1 1721.13
  5129.2  1727.8  5152.5 1734.33  5170.6 1738.29  5189.6 1740.05  5211.4 1740.53
#Mann= 10 ,-1 , 0
  4167.1    .063       0  4293.8    .035       0  4415.1     .07       0
  4619.6    .035       0  4661.1     .07       0  4824.2    .035       0
  4926.5      .1       0  4957.1     .05       0  4962.1      .1       0
  5129.2    .063       0
Bank Sta=4957.1,4962.1
XS Rating Curve= 0 ,0
Exp/Cntr=0.3,0.1

Type RM Length L Ch R = 1 ,4676    ,591,591,591
BEGIN DESCRIPTION:
Nichols Creek 10.0
END DESCRIPTION:
XS GIS Cut Line= 3
      1900125.01     13939275.01      1899705.32      13938951.9
      1899424.97     13938824.98
#Sta/Elev= 30
  4438.2 1714.19  4478.5 1712.78  4501.5 1711.79  4568.7 1708.69  4640.6 1706.96
  4670.9 1708.08  4785.9  1705.9  4872.9 1703.37    4917 1703.35  4931.4  1704.2
  4958.5 1704.11  4969.7  1702.5  4982.9 1702.48    5006 1700.84  5009.8 1699.73
  5010.2 1699.23  5014.8 1699.73  5028.2 1704.13  5061.9 1705.03  5071.8    1707
    5085 1704.82  5113.6 1710.38  5142.8 1713.53  5159.7 1715.28  5200.5 1724.24
  5218.6 1729.07  5229.9 1733.57  5236.7 1734.97  5254.9 1736.29  5275.6 1736.17
#Mann= 8 ,-1 , 0
  4438.2    .035       0  4478.5     .07       0  4501.5    .035       0
  4785.9     .07       0  4931.4      .1       0  5009.8     .05       0
  5014.8      .1       0  5142.8     .07       0
Bank Sta=5009.8,5014.8
XS Rating Curve= 0 ,0
Exp/Cntr=0.3,0.1

Type RM Length L Ch R = 1 ,4085    ,454,454,454
BEGIN DESCRIPTION:
Nichols Creek 9.0
END DESCRIPTION:
XS GIS Cut Line= 3
      1900175.02     13938925.02        1900075.       13938825.
        1899525.       13938575.
#Sta/Elev= 30
  4858.8 1708.03  4876.1 1707.52  4905.9 1704.89    4942 1696.33  4960.9 1695.26
  4971.7 1692.97  4992.4 1691.52  4992.7 1691.02  4997.4 1691.52  5017.3 1700.46
  5025.9 1702.71  5035.4 1703.13  5157.8  1704.2  5190.7 1703.74  5207.2 1702.15
  5293.7  1702.5  5309.3 1701.55  5332.4 1703.65  5355.5 1703.21  5381.8  1705.1
  5391.7 1704.98  5398.9 1706.01    5428 1704.68  5457.6 1705.75  5470.4 1708.13
  5487.3 1709.83  5523.5 1717.03  5538.4 1718.79  5570.1 1722.11  5604.4 1722.82
#Mann= 4 ,-1 , 0
  4858.8    .035       0  4992.4    .035       0  4997.4    .035       0
  5398.9      .1       0
#XS Ineff= 2 , 0
                         5405.99         1706.07
Permanent Ineff=
       F       F
Bank Sta=4992.4,4997.4
XS Rating Curve= 0 ,0
Exp/Cntr=0.3,0.1

Type RM Length L Ch R = 1 ,3631    ,468,468,468
BEGIN DESCRIPTION:
Nichols Creek 8.0
END DESCRIPTION:
XS GIS Cut Line= 4
      1900374.98     13938524.98      1900303.14     13938453.14
      1900241.61     13938431.28      1899708.13     13938425.57
#Sta/Elev= 30
    4854 1708.27  4874.2 1708.05  4908.3 1704.82  4927.2 1698.79  4962.6 1692.75
  4980.5  1690.4  4999.7 1688.93  5012.2 1685.49    5013 1684.97  5013.4 1684.47
  5018.1 1684.97  5018.8 1686.16  5029.3 1693.36  5033.9 1695.39  5038.2 1696.13
  5060.9  1697.3  5173.6  1698.3  5198.5 1697.52  5254.9 1698.26  5272.7 1698.16
  5279.9  1697.4  5312.9 1698.08  5327.9 1697.48  5346.9 1699.01  5400.3 1700.29
  5456.9 1700.14  5471.9 1702.29  5501.3 1700.84  5525.9 1702.41  5554.4  1702.3
#Mann= 5 ,-1 , 0
    4854      .1       0  5012.2    .035       0    5013     .05       0
  5018.1    .035       0  5173.6    .094       0
#XS Ineff= 2 , 0
                         5408.19         1700.96
Permanent Ineff=
       F       F
Bank Sta=5013,5018.1
XS Rating Curve= 0 ,0
Exp/Cntr=0.3,0.1

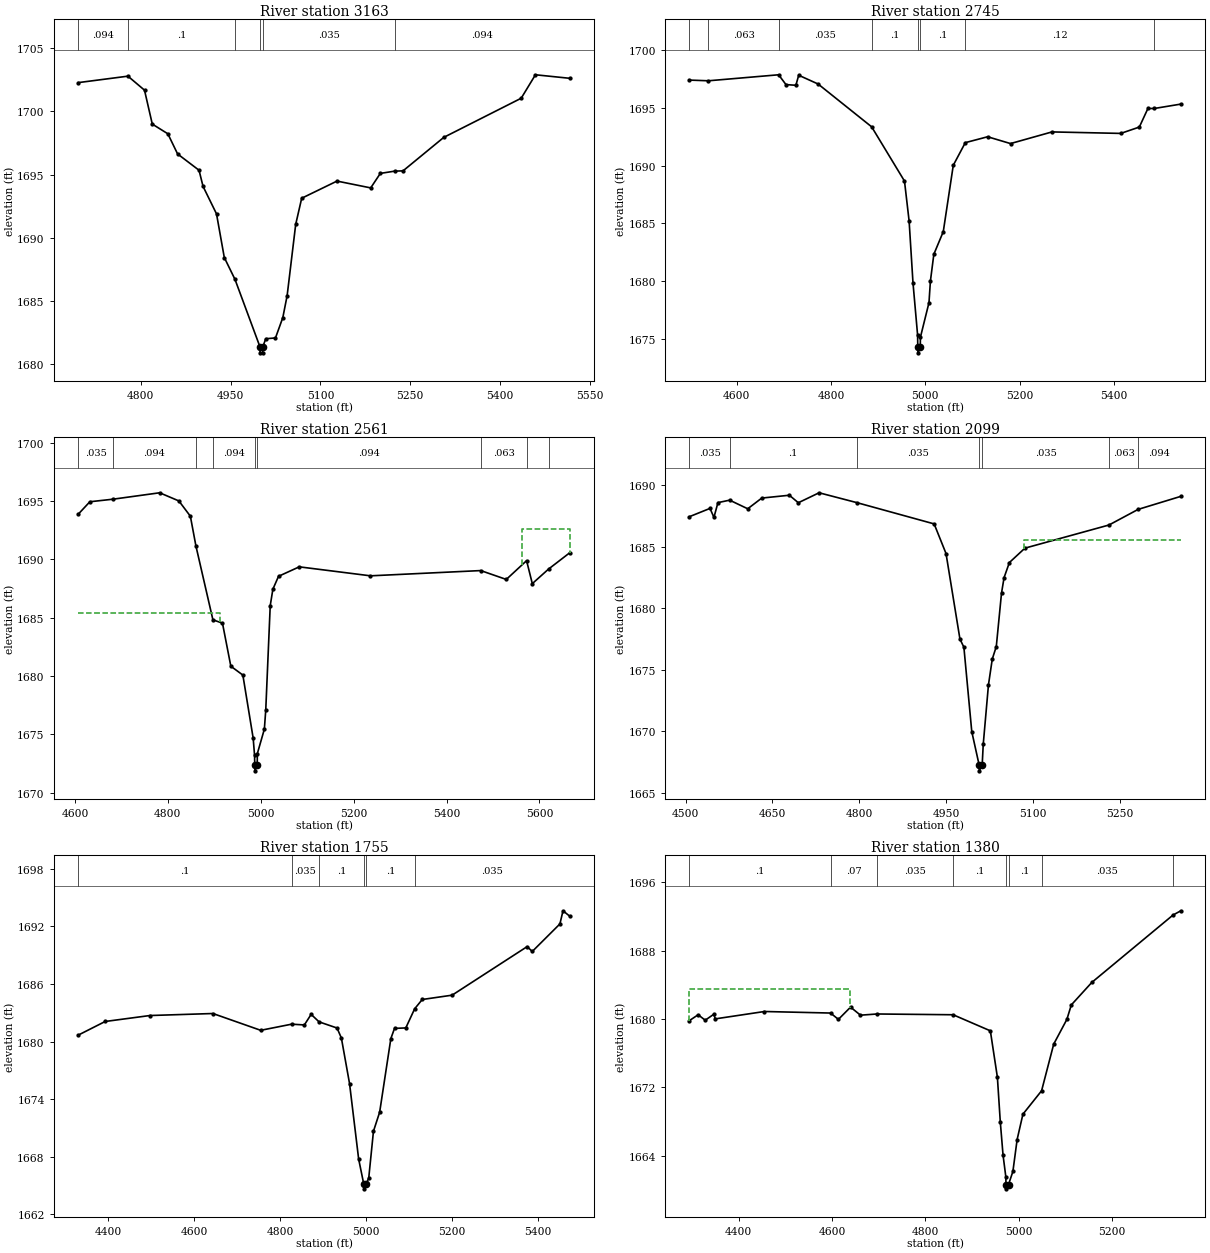
Type RM Length L Ch R = 1 ,3163    ,418,418,418
BEGIN DESCRIPTION:
Nichols Creek 7.0
END DESCRIPTION:
XS GIS Cut Line= 3
      1900405.46     13938007.68        1900125.       13938125.
      1899692.56     13938408.15
#Sta/Elev= 30
  4695.7 1702.29  4778.4  1702.8  4806.1 1701.69  4819.1    1699  4845.1 1698.23
  4861.4 1696.63  4897.2 1695.34  4903.9 1694.06  4926.4 1691.88  4939.4 1688.42
  4957.3 1686.68  4998.8 1681.36  4999.2 1680.86  5003.5 1680.86  5003.9 1681.36
  5008.7 1681.98  5024.9 1682.04  5037.2 1683.66  5044.4  1685.4  5058.7 1691.05
  5068.7 1693.12  5127.7 1694.48    5184 1693.94  5200.1 1695.09  5224.2 1695.27
    5238 1695.29  5306.2 1697.95  5435.4 1701.05  5459.2 1702.91  5516.6 1702.63
#Mann= 6 ,-1 , 0
  4695.7    .094       0  4778.4      .1       0  4957.3    .035       0
  4998.8    .035       0  5003.9    .035       0  5224.2    .094       0
Bank Sta=4998.8,5003.9
XS Rating Curve= 0 ,0
Exp/Cntr=0.3,0.1

Type RM Length L Ch R = 1 ,2745    ,184,184,184
BEGIN DESCRIPTION:
Nichols Creek 6.0
END DESCRIPTION:
XS GIS Cut Line= 3
       1900625.1     13937774.69        1900125.       13937775.
      1899589.57      13937854.5
#Sta/Elev= 30
  4500.3 1697.41  4540.5 1697.35  4689.2 1697.87  4704.8 1697.02  4725.8 1696.96
  4731.8 1697.83  4772.9 1697.07  4886.4 1693.36    4956 1688.66  4965.8  1685.2
    4974 1679.85  4983.8 1675.31  4984.1 1674.28  4984.5 1673.78  4989.4 1674.28
  4989.8 1675.14  5007.9 1678.13  5010.9 1679.99  5018.2 1682.32  5038.2 1684.28
  5059.4 1690.03  5084.9 1691.99  5132.2  1692.5  5180.7 1691.91  5268.7 1692.92
  5414.3 1692.79  5453.7 1693.34  5471.9 1694.95  5485.4 1694.95  5541.7 1695.33
#Mann= 8 ,-1 , 0
  4500.3    .094       0  4540.5    .063       0  4689.2    .035       0
  4886.4      .1       0  4984.1     .05       0  4989.4      .1       0
  5084.9     .12       0  5485.4    .094       0
Bank Sta=4984.1,4989.4
XS Rating Curve= 0 ,0
Exp/Cntr=0.3,0.1

Type RM Length L Ch R = 1 ,2561    ,462,462,462
BEGIN DESCRIPTION:
Nichols Creek 5.1
END DESCRIPTION:
XS GIS Cut Line= 3
      1900517.13     13937566.89      1899733.15     13937615.01
      1899460.91     13937622.44
#Sta/Elev= 30
  4607.6 1693.89  4632.2 1694.94  4682.1 1695.16  4782.5 1695.71  4823.9 1695.01
  4848.6  1693.7  4860.6 1691.14  4897.1 1684.82  4917.7 1684.53  4935.7 1680.84
  4961.6 1680.08  4983.8 1674.67  4986.8 1673.19  4987.2 1672.37  4987.6 1671.87
  4992.5 1672.37  4992.8 1673.35  5007.9 1675.45  5010.9  1677.1  5020.5 1686.03
  5026.2 1687.44  5038.4 1688.55    5083 1689.36  5236.3 1688.59  5473.7 1689.04
  5528.7 1688.28  5572.4 1689.89  5584.7 1687.92  5619.7 1689.17  5665.4 1690.57
#Mann= 9 ,-1 , 0
  4607.6    .035       0  4682.1    .094       0  4860.6    .035       0
  4897.1    .094       0  4987.2     .05       0  4992.5    .094       0
  5473.7    .063       0  5572.4    .035       0  5619.7    .063       0
#XS Ineff= 2 , 0
         4911.69 1685.39 5561.44         1692.63
Permanent Ineff=
       F       F
Bank Sta=4987.2,4992.5
XS Rating Curve= 0 ,0
Exp/Cntr=0.3,0.1

Type RM Length L Ch R = 1 ,2099    ,344,344,344
BEGIN DESCRIPTION:
Nichols Creek 5.0
END DESCRIPTION:
XS GIS Cut Line= 4
      1900325.61     13937106.41      1900172.22     13937190.64
      1899890.55      13937345.3      1899656.88     13937607.71
#Sta/Elev= 30
  4506.8 1687.44  4542.2 1688.11    4549 1687.38  4555.9 1688.58  4576.1 1688.78
  4607.3 1688.08  4631.5 1688.95  4679.1 1689.18  4694.6 1688.57  4730.4 1689.38
  4795.5 1688.58  4928.9 1686.85  4949.4 1684.44  4973.4 1677.49  4980.2 1676.83
  4993.8 1669.97  5006.4 1667.28  5006.8 1666.78  5011.8 1667.28  5013.6 1668.94
  5022.6 1673.77  5029.2 1675.87  5036.1 1676.88  5045.1 1681.22  5049.5 1682.48
  5058.7 1683.71  5085.5 1684.88  5230.5 1686.76  5280.8 1688.03  5354.5 1689.09
#Mann= 7 ,-1 , 0
  4506.8    .035       0  4576.1      .1       0  4795.5    .035       0
  5006.4    .035       0  5011.8    .035       0  5230.5    .063       0
  5280.8    .094       0
#XS Ineff= 2 , 0
                         5083.32         1685.56
Permanent Ineff=
       F       F
Bank Sta=5006.4,5011.8
XS Rating Curve= 0 ,0
Exp/Cntr=0.3,0.1

Type RM Length L Ch R = 1 ,1755    ,375,375,375
BEGIN DESCRIPTION:
Nichols Creek 4.0
END DESCRIPTION:
XS GIS Cut Line= 4
       1900212.4     13936865.04      1899944.29     13936998.77
      1899605.81     13937167.61       1899234.6     13937449.54
#Sta/Elev= 30
  4330.9 1680.69  4393.2  1682.1  4497.2 1682.72    4644 1682.93  4755.3 1681.18
  4827.3 1681.82  4856.9 1681.74  4872.7 1682.84  4891.2 1682.06    4933 1681.42
  4943.1 1680.38  4962.1 1675.64  4983.3 1667.78  4995.2 1665.17  4995.6 1664.67
  5000.6 1665.17  5006.8 1665.79  5017.8 1670.67  5032.2 1672.65  5058.3 1680.32
  5066.8 1681.38  5093.1 1681.43  5113.7 1683.42  5131.4 1684.39  5200.9 1684.84
  5375.7  1689.9  5387.5 1689.39  5451.9 1692.26  5459.1 1693.63  5474.9 1693.06
#Mann= 6 ,-1 , 0
  4330.9      .1       0  4827.3    .035       0  4891.2      .1       0
  4995.2     .05       0  5000.6      .1       0  5113.7    .035       0
Bank Sta=4995.2,5000.6
XS Rating Curve= 0 ,0
Exp/Cntr=0.3,0.1

Type RM Length L Ch R = 1 ,1380    ,450,450,450
BEGIN DESCRIPTION:
Nichols Creek 3.0
END DESCRIPTION:
XS GIS Cut Line= 4
      1900175.04     13936785.33      1899813.34     13936831.66
        1899475.       13936875.      1899143.32     13936977.45
#Sta/Elev= 30
  4294.4 1679.82    4313  1680.5  4328.1 1679.86  4346.3 1680.55  4349.9 1680.02
  4455.1 1680.88  4596.7  1680.7  4613.5 1679.96  4639.6 1681.39  4660.8 1680.45
  4696.5 1680.59  4859.3  1680.5  4939.1 1678.62  4954.2 1673.19  4960.4 1667.98
  4966.3 1664.09  4972.3 1661.53  4972.6 1660.64    4973 1660.14    4978 1660.64
  4987.4 1662.17  4996.5 1665.91  5008.9 1668.87  5048.9 1671.61  5074.9 1677.07
  5103.1 1679.96  5112.6 1681.65  5156.5 1684.28  5330.5 1692.16  5347.3 1692.66
#Mann= 8 ,-1 , 0
  4294.4      .1       0  4596.7     .07       0  4696.5    .035       0
  4859.3      .1       0  4972.6     .05       0    4978      .1       0
  5048.9    .035       0  5330.5    .063       0
#XS Ineff= 2 , 0
         4638.76 1683.54
Permanent Ineff=
       F       F
Bank Sta=4972.6,4978
XS Rating Curve= 0 ,0
Exp/Cntr=0.3,0.1