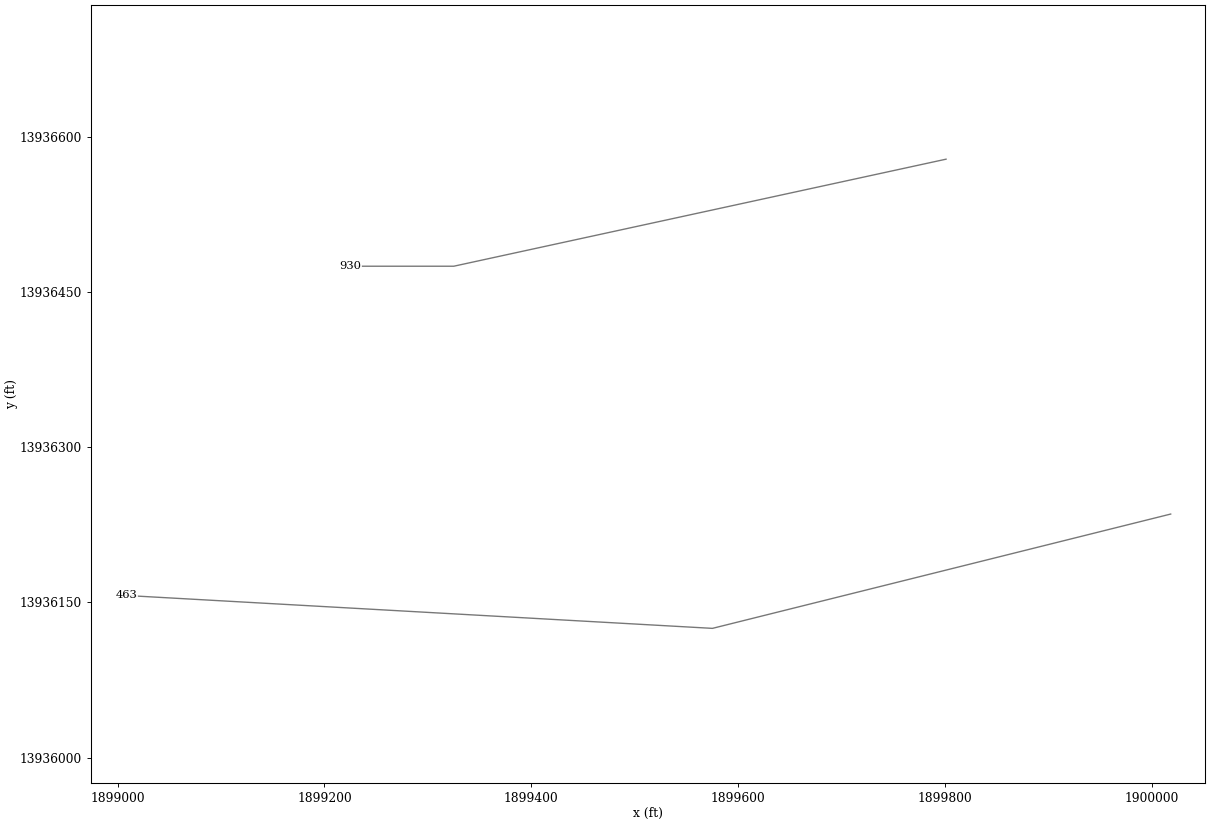
HEC-RAS study Nichols Creek.prj: Nichols Creek Base Level Engineering

--- Nichols Creek.g01 (geometry) --- (continued)

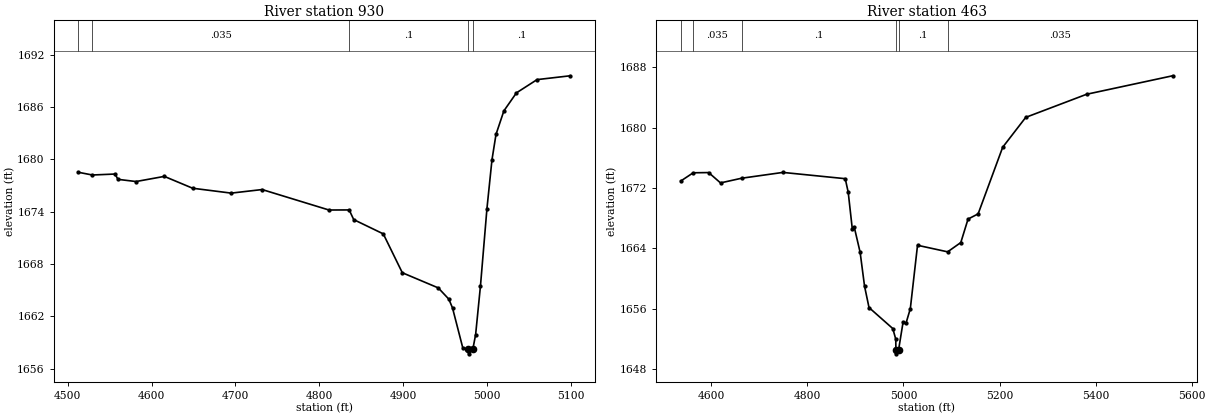
Type RM Length L Ch R = 1 ,930     ,467,467,467
BEGIN DESCRIPTION:
Nichols Creek 2.0
END DESCRIPTION:
XS GIS Cut Line= 3
      1899800.77     13936578.45        1899325.       13936475.
      1899224.99       13936475.
#Sta/Elev= 30
  4512.7 1678.53  4529.3 1678.22  4556.3 1678.33  4559.9 1677.72  4581.4 1677.47
  4615.2 1678.06    4649  1676.7    4695 1676.14  4731.9 1676.55  4811.7  1674.2
  4835.8 1674.21  4841.2  1673.1  4876.5 1671.46  4899.2    1667  4942.1 1665.26
  4954.7 1663.97  4959.1 1662.96  4971.3  1658.4  4977.8 1658.19  4978.2 1657.69
  4983.3 1658.19  4986.7 1659.91  4992.5 1665.53  5000.2 1674.37  5006.2 1679.97
    5011 1682.88  5020.4 1685.58  5035.4 1687.65    5060 1689.17  5099.6 1689.61
#Mann= 5 ,-1 , 0
  4512.7     .07       0  4529.3    .035       0  4835.8      .1       0
  4977.8     .05       0  4983.3      .1       0
Bank Sta=4977.8,4983.3
XS Rating Curve= 0 ,0
Exp/Cntr=0.3,0.1

Type RM Length L Ch R = 1 ,463     ,0,0,0
BEGIN DESCRIPTION:
Nichols Creek 1.0
END DESCRIPTION:
XS GIS Cut Line= 3
      1900017.88     13936235.48        1899575.       13936125.
      1899008.34     13936156.78
#Sta/Elev= 30
  4536.3 1672.93  4562.1 1674.02  4594.3 1674.05    4619 1672.68  4662.9  1673.3
  4748.9 1674.07  4878.7 1673.24  4884.9 1671.44  4893.4 1666.58  4897.3 1666.87
  4909.7 1663.49  4918.9    1659  4928.2 1656.17  4977.7 1653.39  4983.9 1651.98
  4984.2 1650.54  4984.7 1650.04  4989.7 1650.54  4999.1 1654.23  5005.2 1654.09
  5014.2 1656.02  5029.2 1664.42  5091.9 1663.55  5119.3 1664.78  5134.4 1667.89
  5155.4 1668.58  5206.5  1677.4  5254.5 1681.36  5381.2 1684.42  5560.3 1686.87
#Mann= 6 ,-1 , 0
  4536.3     .07       0  4562.1    .035       0  4662.9      .1       0
  4984.2     .05       0  4989.7      .1       0  5091.9    .035       0
Bank Sta=4984.2,4989.7
XS Rating Curve= 0 ,0
Exp/Cntr=0.3,0.1

Chan Stop Cuts=-1
Use User Specified Reach Order=0
Composite Channel Slope=5