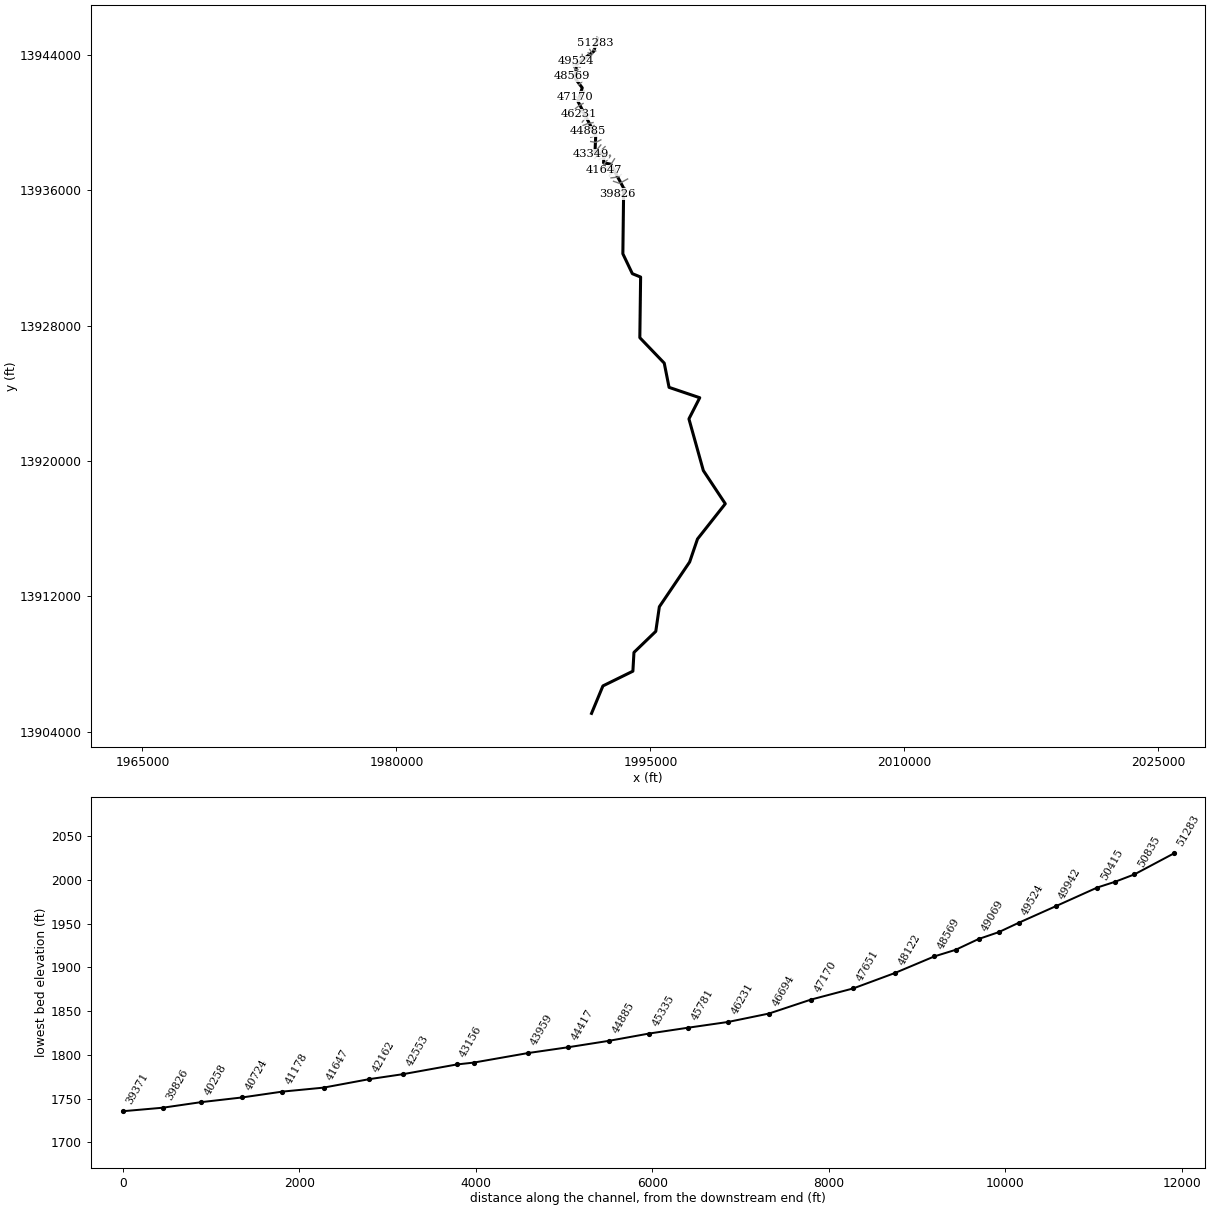
--- North Creek.prj (project) ---

Proj Title=North Creek Base Level Engineering
Current Plan=p01
Default Exp/Contr=0.3,0.1
English Units
Geom File=g01
Flow File=f01
Plan File=p01
Y Axis Title=Elevation
X Axis Title(PF)=Main Channel Distance
X Axis Title(XS)=Station
BEGIN DESCRIPTION:
North Creek
END DESCRIPTION:
DSS Export Rating Curves= 0
DSS Export Rating Curve Sorted= 0
DSS Export Volume Flow Curves= 0
DXF OffsetX= 0
DXF OffsetY= 0
DXF ScaleX= 1
DXF ScaleY= 10

--- North Creek.p01 (plan) ---

Plan Title=Multiple Run
Short Identifier=Multiple
Geom File=g01
Flow File=f01
Subcritical Flow
K Sum by GR= 0
Std Step Tol= 0.01
Critical Tol= 0.01
Num of Std Step Trials= 20
Max Error Tol= 0.3
Flow Tol Ratio= 0.001
Split Flow NTrial= 30
Split Flow Tol= 0.02
Split Flow Ratio= 0.02
Log Output Level= 0
Friction Slope Method= 1
Unsteady Friction Slope Method= 2
Unsteady Bridges Friction Slope Method= 1
Parabolic Critical Depth
Global Vel Dist=  1 , 1 , 1
Global Log Level= 0
CheckData=True
Encroach Param= -1, 0, 0, 0
BEGIN DESCRIPTION:
Multiple Run
END DESCRIPTION:

--- North Creek.f01 (steady flow) ---

Flow Title=Multiple
Program Version=4.10
Number of Profiles= 7
Profile Names=10-year,25-year,50-year,1pct_min,100-year,1pct_plu,500-year
River Rch & RM=North Creek,Reach-1         ,51283
     612    1024    1411     947    1889    3768    3349
River Rch & RM=North Creek,Reach-1         ,46231
     994    1707    2393    1629    3251    6487    5949
River Rch & RM=North Creek,Reach-1         ,41178
    1515    2657    3778    2603    5195   10364    9746
River Rch & RM=North Creek,Reach-1         ,36450
    2327    4159    5991    4175    8329   16619   15989
River Rch & RM=North Creek,Reach-1         ,31534
    3154    5712    8300    5828   11629   23202   22675
River Rch & RM=North Creek,Reach-1         ,28225
    3842    7015   10249    7232   14429   28790   28408
River Rch & RM=North Creek,Reach-1         ,25936
    3921    7157   10455    7374   14714   29358   28951
River Rch & RM=North Creek,Reach-1         ,24153
    4354    7973   11670    8246   16452   32826   32481
River Rch & RM=North Creek,Reach-1         ,21242
    4672    8541   12490    8816   17591   35098   34644
River Rch & RM=North Creek,Reach-1         ,19328
    4846    8854   12944    9130   18218   36349   35832
River Rch & RM=North Creek,Reach-1         ,14352
    4980    9104   13313    9393   18742   37396   36880
River Rch & RM=North Creek,Reach-1         ,13113
    5463    9985   14599   10294   20539   40981   40365
River Rch & RM=North Creek,Reach-1         ,2459
    6743   12397   18192   12853   25645   51169   50514
Boundary for River Rch & Prof#=North Creek,Reach-1         , 1
Up Type= 0
Dn Type= 3
Dn Slope=0.006
Boundary for River Rch & Prof#=North Creek,Reach-1         , 2
Up Type= 0
Dn Type= 3
Dn Slope=0.006
Boundary for River Rch & Prof#=North Creek,Reach-1         , 3
Up Type= 0
Dn Type= 3
Dn Slope=0.006
Boundary for River Rch & Prof#=North Creek,Reach-1         , 4
Up Type= 0
Dn Type= 3
Dn Slope=0.006
Boundary for River Rch & Prof#=North Creek,Reach-1         , 5
Up Type= 0
Dn Type= 3
Dn Slope=0.006
Boundary for River Rch & Prof#=North Creek,Reach-1         , 6
Up Type= 0
Dn Type= 3
Dn Slope=0.006
Boundary for River Rch & Prof#=North Creek,Reach-1         , 7
Up Type= 0
Dn Type= 3
Dn Slope=0.006
DSS Import GetInterval= 0
DSS Import GetPeak= 0
DSS Import FillOption= 0

--- North Creek.g01 (geometry) ---

Geom Title=Existing Conditions
Program Version=4.10

River Reach=North Creek     ,Reach-1
Reach XY= 30
        1991875.       13944975.      1991661.53     13944211.43
      1990627.07     13943419.14      1990577.06     13942580.85
      1990975.24     13942050.08      1990725.24     13941240.22
      1991771.96     13939223.58      1991730.08     13938272.69
      1992264.53     13938084.83      1992234.13     13937618.22
      1992664.37       13937535.      1993422.75     13936119.07
      1993375.07     13932240.39      1993935.65       13931065.
      1994423.95     13930864.58      1994377.26     13927280.94
      1995819.17      13925777.3      1996104.58     13924344.77
      1997915.87     13923731.72      1997277.17     13922480.97
      1998128.83     13919426.58      1999425.55     13917464.81
      1997783.16     13915381.05      1997319.48     13914022.57
      1995530.84     13911377.29      1995319.46     13909922.58
      1994030.48     13908677.44      1993967.19     13907568.81
      1992197.88     13906698.52        1991525.       13905075.

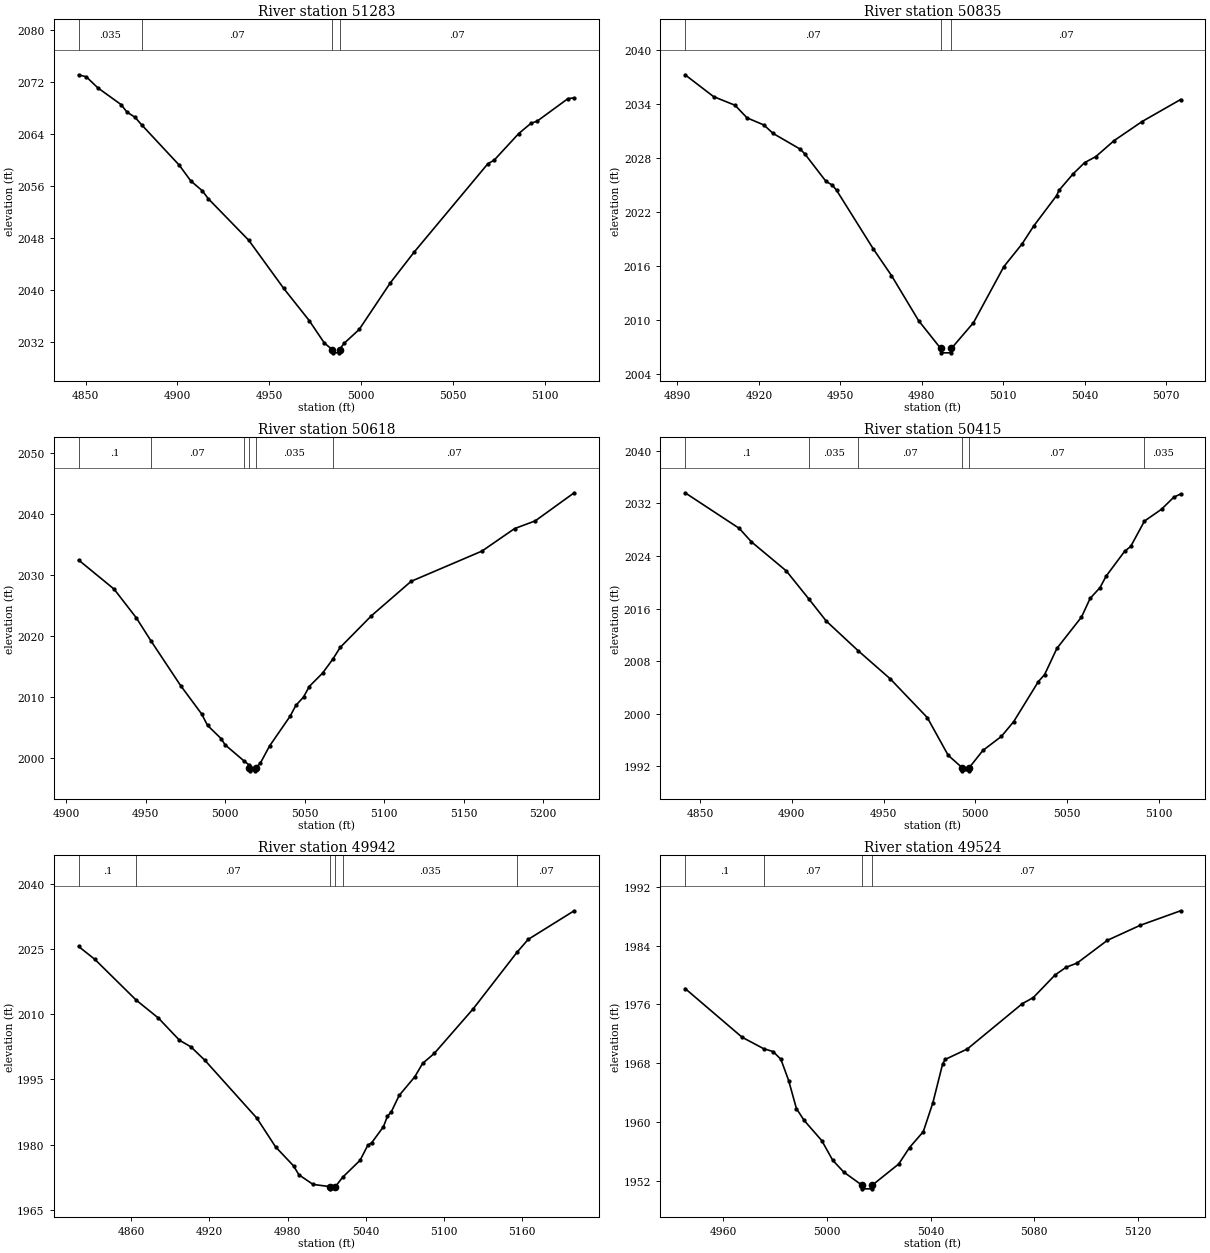
Type RM Length L Ch R = 1 ,51283   ,448,448,448
BEGIN DESCRIPTION:
North Creek 105.0
END DESCRIPTION:
XS GIS Cut Line= 3
        1991975.       13944625.        1991825.       13944675.
      1991725.01     13944724.99
#Sta/Elev= 30
  4846.2 2073.11  4850.4 2072.79  4856.7 2071.09  4869.3 2068.53  4872.5 2067.38
  4876.9 2066.58  4880.5 2065.42    4901 2059.21  4907.3 2056.78  4913.6 2055.26
  4916.8 2054.05  4938.9 2047.64  4957.9 2040.25  4971.8  2035.3    4980 2031.86
  4984.3 2030.84  4984.6 2030.34  4988.1 2030.34  4988.3 2030.84  4990.7 2031.78
    4999 2033.93    5016 2041.12  5028.9 2045.82  5069.1 2059.43  5072.5 2059.97
  5085.9 2064.07  5092.6 2065.65  5095.9 2065.97  5112.7 2069.44  5116.1 2069.56
#Mann= 4 ,-1 , 0
  4846.2    .035       0  4880.5     .07       0  4984.3     .05       0
  4988.3     .07       0
Bank Sta=4984.3,4988.3
XS Rating Curve= 0 ,0
Exp/Cntr=0.3,0.1

Type RM Length L Ch R = 1 ,50835   ,217,217,217
BEGIN DESCRIPTION:
North Creek 104.0
END DESCRIPTION:
XS GIS Cut Line= 3
      1991774.99     13944225.01        1991675.       13944275.
        1991625.       13944325.
#Sta/Elev= 30
  4892.8 2037.24  4903.3 2034.81  4911.2 2033.85  4915.6 2032.45  4921.8 2031.66
  4925.2 2030.72  4935.2 2028.97  4936.9 2028.44  4944.7 2025.38    4947 2024.98
  4948.6 2024.39  4962.1 2017.88  4968.8 2014.92  4978.8  2009.9  4986.9 2006.82
  4987.1 2006.32  4990.6 2006.32  4990.9 2006.82    4999 2009.67  5010.2 2015.91
  5016.9 2018.43  5021.2 2020.43  5029.6  2023.8  5030.5 2024.39  5035.6 2026.19
  5039.9 2027.46  5044.1 2028.15  5050.8 2029.92  5061.1 2032.04  5075.3 2034.49
#Mann= 3 ,-1 , 0
  4892.8     .07       0  4986.9     .05       0  4990.9     .07       0
Bank Sta=4986.9,4990.9
XS Rating Curve= 0 ,0
Exp/Cntr=0.3,0.1

Type RM Length L Ch R = 1 ,50618   ,203,203,203
BEGIN DESCRIPTION:
Mapping XS f594865e
END DESCRIPTION:
XS GIS Cut Line= 2
      1991585.59     13944059.43      1991417.86     13944322.27
#Sta/Elev= 30
  4907.7 2032.44    4930 2027.69    4944 2022.98  4953.3 2019.18  4971.9 2011.89
  4985.1 2007.26  4988.8 2005.39  4997.4 2003.21  4999.8 2002.22  5011.5 1999.63
  5014.8 1998.94  5015.2 1998.45  5015.4 1997.95  5018.9 1997.95  5019.2 1998.45
  5022.1 1999.24  5027.8    2002  5040.8  2006.9  5044.4 2008.67  5049.2 2010.01
  5052.8 2011.75  5061.2 2013.94  5067.7 2016.25  5072.3 2018.15  5091.9 2023.32
  5116.9 2028.96  5161.5 2033.91    5182 2037.59    5195 2038.85  5219.5 2043.45
#Mann= 6 ,-1 , 0
  4907.7      .1       0  4953.3     .07       0  5011.5    .035       0
  5015.2     .05       0  5019.2    .035       0  5067.7     .07       0
Bank Sta=5015.2,5019.2
XS Rating Curve= 0 ,0
Exp/Cntr=0.3,0.1

Type RM Length L Ch R = 1 ,50415   ,473,473,473
BEGIN DESCRIPTION:
North Creek 103.0
END DESCRIPTION:
XS GIS Cut Line= 3
      1991524.98     13943975.01        1991375.       13944025.
        1991325.       13944125.
#Sta/Elev= 30
  4841.9 2033.59  4871.4 2028.18    4878 2026.14    4897 2021.72  4909.5 2017.38
  4918.8 2014.09  4936.1  2009.6  4953.6 2005.32  4973.8 1999.43  4985.2 1993.69
  4992.7 1991.83  4992.9 1991.33  4996.4 1991.33  4996.7 1991.83  5004.1 1994.43
  5014.2 1996.57  5020.9 1998.82  5034.3 2004.89  5037.7 2005.95  5044.4 2009.94
  5057.8  2014.7  5062.5 2017.54  5067.9 2019.18  5071.2 2020.91  5081.3  2024.7
  5084.6 2025.43  5092.1 2029.29  5101.4 2031.09  5108.1 2032.93  5111.8  2033.4
#Mann= 6 ,-1 , 0
  4841.9      .1       0  4909.5    .035       0  4936.1     .07       0
  4992.7     .05       0  4996.7     .07       0  5092.1    .035       0
Bank Sta=4992.7,4996.7
XS Rating Curve= 0 ,0
Exp/Cntr=0.3,0.1

Type RM Length L Ch R = 1 ,49942   ,418,418,418
BEGIN DESCRIPTION:
North Creek 102.0
END DESCRIPTION:
XS GIS Cut Line= 3
      1991074.99     13943675.02        1990975.       13943825.
        1990975.     13944025.04
#Sta/Elev= 30
  4819.7 2025.54  4832.2 2022.57  4863.9 2013.21  4880.9  2009.1  4897.1 2003.99
  4905.9 2002.47  4916.7 1999.35  4956.5 1986.08  4970.8  1979.5  4984.6 1975.13
  4988.8 1973.05  4999.6 1970.86  5012.7 1970.34  5012.9 1969.84  5016.7 1970.34
  5022.3  1972.5  5035.7  1976.4  5041.6 1979.84  5044.7 1980.47  5053.6 1984.11
  5056.7 1986.52  5059.7 1987.57  5065.7 1991.31  5077.7  1995.6  5083.7 1998.67
  5092.7 2000.98  5122.6 2011.25  5156.1  2024.2  5164.7 2027.17    5200 2033.75
#Mann= 6 ,-1 , 0
  4819.7      .1       0  4863.9     .07       0  5012.7     .05       0
  5016.7     .07       0  5022.3    .035       0  5156.1     .07       0
Bank Sta=5012.7,5016.7
XS Rating Curve= 0 ,0
Exp/Cntr=0.3,0.1

Type RM Length L Ch R = 1 ,49524   ,225,225,225
BEGIN DESCRIPTION:
North Creek 101.0
END DESCRIPTION:
XS GIS Cut Line= 3
      1990775.01       13943525.        1990725.       13943525.
      1990625.03     13943624.97
#Sta/Elev= 30
  4945.2 1978.17  4967.2 1971.56  4975.5 1970.01  4979.2 1969.61  4982.2 1968.56
  4985.2 1965.68  4988.2 1961.87  4991.2 1960.26    4998 1957.52  5002.2 1954.87
  5006.5 1953.25  5013.5 1951.48  5013.7 1950.98  5017.2 1950.98  5017.5 1951.48
  5027.7 1954.35  5031.9 1956.59  5037.2 1958.74  5040.9 1962.66  5044.7 1967.97
  5045.7 1968.55  5054.2 1969.96  5075.4  1976.1  5079.7 1976.94  5088.1 1980.01
  5092.4 1981.06  5096.6 1981.62  5108.3 1984.71    5121 1986.75  5136.6 1988.72
#Mann= 4 ,-1 , 0
  4945.2      .1       0  4975.5     .07       0  5013.5     .05       0
  5017.5     .07       0
Bank Sta=5013.5,5017.5
XS Rating Curve= 0 ,0
Exp/Cntr=0.3,0.1

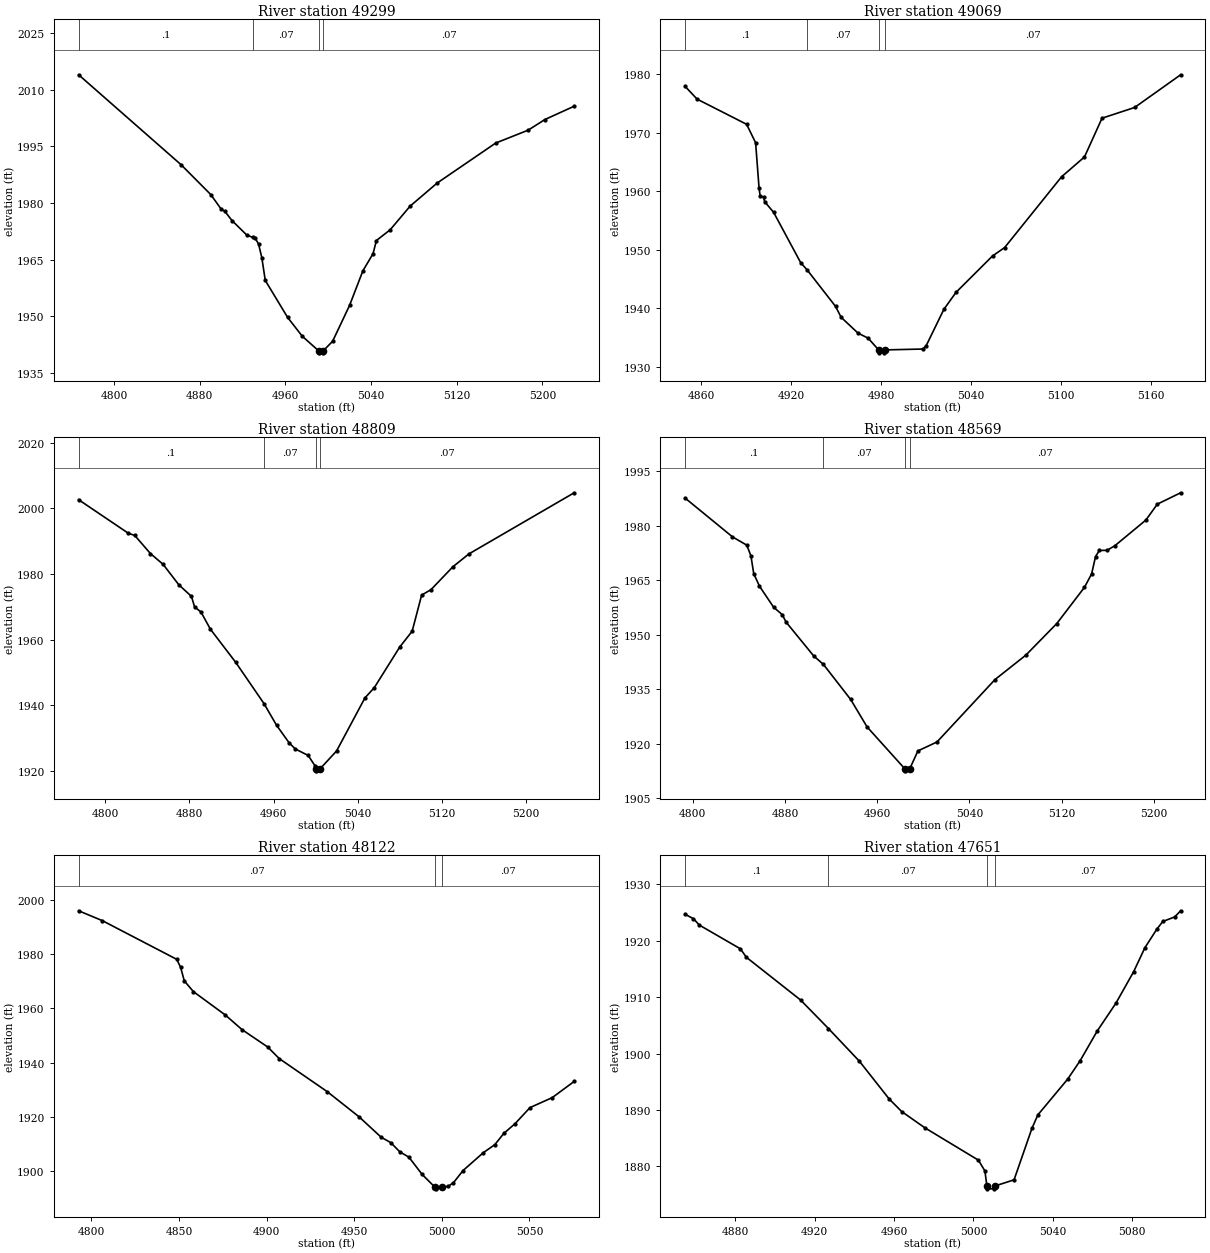
Type RM Length L Ch R = 1 ,49299   ,230,230,230
BEGIN DESCRIPTION:
Mapping XS 0f06c7dc
END DESCRIPTION:
XS GIS Cut Line= 2
      1990847.12     13943268.77      1990406.04     13943408.89
#Sta/Elev= 30
  4766.8 2013.94  4862.4 1990.16  4890.2 1982.24  4900.1 1978.31  4903.3 1977.83
    4910 1975.37  4923.7 1971.56  4929.2 1970.92  4931.6 1970.69  4934.8 1969.19
  4937.9 1965.52  4941.1 1959.52  4961.9 1949.76  4975.7 1944.73  4991.1 1940.85
  4991.3 1940.35  4994.8 1940.35  4995.1 1940.85    5004 1943.41  5019.8 1952.88
  5032.3 1962.07  5041.8 1966.61  5044.9 1970.08  5057.7  1972.9  5076.4 1979.18
  5101.6 1985.28  5156.3 1995.87  5186.6 1999.28  5202.3  2002.1  5229.6 2005.62
#Mann= 4 ,-1 , 0
  4766.8      .1       0  4929.2     .07       0  4991.1     .05       0
  4995.1     .07       0
Bank Sta=4991.1,4995.1
XS Rating Curve= 0 ,0
Exp/Cntr=0.3,0.1

Type RM Length L Ch R = 1 ,49069   ,260,260,260
BEGIN DESCRIPTION:
North Creek 100.0
END DESCRIPTION:
XS GIS Cut Line= 3
      1990725.01       13943125.        1990575.       13943125.
      1990474.99     13943275.01
#Sta/Elev= 30
  4849.3 1977.94  4857.3 1975.76  4890.3 1971.46  4896.3 1968.31  4898.6 1960.57
  4899.3 1959.26  4901.6 1958.99  4902.3 1958.25  4908.3 1956.42  4926.3 1947.84
  4930.7 1946.56  4949.6 1940.34  4953.3 1938.48  4964.6 1935.77  4971.3 1934.92
  4978.3 1932.91  4978.5 1932.41    4982 1932.41  4982.3 1932.91  5007.7 1933.06
  5009.9 1933.58  5021.8 1939.85  5029.9 1942.75  5054.2 1948.96  5062.3  1950.4
  5100.2 1962.48  5115.5 1965.88  5127.2  1972.5  5148.9 1974.33  5179.6 1979.92
#Mann= 4 ,-1 , 0
  4849.3      .1       0  4930.7     .07       0  4978.3     .05       0
  4982.3     .07       0
Bank Sta=4978.3,4982.3
XS Rating Curve= 0 ,0
Exp/Cntr=0.3,0.1

Type RM Length L Ch R = 1 ,48809   ,240,240,240
BEGIN DESCRIPTION:
Mapping XS 0f425970
END DESCRIPTION:
XS GIS Cut Line= 2
      1990800.49     13942866.27      1990328.79     13942864.06
#Sta/Elev= 30
  4774.5 2002.59  4821.9 1992.36  4827.9 1991.72  4842.9 1986.18  4854.9 1982.92
  4869.9 1976.68  4881.9 1973.17  4884.9 1969.93  4890.9 1968.44  4899.9 1963.19
  4923.9 1953.14  4950.9 1940.55  4962.9 1933.94  4974.9 1928.57  4980.9 1926.69
    4993 1924.75  4999.5 1921.58    5000 1920.56  5000.2 1920.06    5004 1920.56
    5020  1926.1    5047 1942.24    5056 1945.41  5080.1 1957.72    5092 1962.57
    5101 1973.56  5109.9 1975.21  5130.8 1982.19    5146 1986.09  5246.2  2004.7
#Mann= 4 ,-1 , 0
  4774.5      .1       0  4950.9     .07       0    5000     .05       0
    5004     .07       0
Bank Sta=5000,5004
XS Rating Curve= 0 ,0
Exp/Cntr=0.3,0.1

Type RM Length L Ch R = 1 ,48569   ,447,447,447
BEGIN DESCRIPTION:
North Creek 99.0
END DESCRIPTION:
XS GIS Cut Line= 3
      1990774.95     13942674.99        1990575.       13942625.
      1990375.01     13942724.99
#Sta/Elev= 30
  4793.4 1987.67  4834.5 1976.99  4846.9 1974.71  4850.5 1971.74  4852.9 1966.89
  4857.9 1963.41  4870.2 1957.61  4877.7 1955.56  4880.9 1953.55  4904.9 1944.22
  4913.4 1941.86    4937 1932.22  4951.2 1924.67  4984.1 1913.08  4984.3 1912.58
  4988.1 1913.08  4995.3 1918.07  5011.8 1920.52  5062.1  1937.7  5088.9 1944.44
  5115.7 1953.13  5139.7  1963.1  5145.9 1966.79  5149.3 1971.56  5152.6 1973.25
  5159.3 1973.29  5166.1 1974.56  5192.9  1981.6  5202.9    1986  5223.1 1989.13
#Mann= 4 ,-1 , 0
  4793.4      .1       0  4913.4     .07       0  4984.1     .05       0
  4988.1     .07       0
Bank Sta=4984.1,4988.1
XS Rating Curve= 0 ,0
Exp/Cntr=0.3,0.1

Type RM Length L Ch R = 1 ,48122   ,471,471,471
BEGIN DESCRIPTION:
North Creek 98.0
END DESCRIPTION:
XS GIS Cut Line= 3
      1990974.99     13942424.99        1990825.       13942275.
      1990775.02     13942225.02
#Sta/Elev= 30
  4792.7 1995.88  4806.3 1992.23  4848.7 1978.01  4850.9 1975.09    4853  1970.1
  4858.2 1966.14  4876.3 1957.59    4886 1952.14  4900.6 1945.77  4907.2  1941.5
  4934.5 1929.38  4952.7 1920.11  4965.4 1912.55  4970.8 1910.61    4976 1907.21
  4981.2 1905.23  4988.7 1898.92  4996.2 1894.09  4996.4 1893.59  5000.2 1894.09
  5003.6 1894.53  5006.6 1895.84  5012.1 1900.33  5023.6 1906.86  5030.2 1909.84
  5035.4 1914.01  5041.8 1917.59  5050.3 1923.48    5063 1927.15  5075.5 1933.11
#Mann= 3 ,-1 , 0
  4792.7     .07       0  4996.2     .05       0  5000.2     .07       0
Bank Sta=4996.2,5000.2
XS Rating Curve= 0 ,0
Exp/Cntr=0.3,0.1

Type RM Length L Ch R = 1 ,47651   ,481,481,481
BEGIN DESCRIPTION:
North Creek 97.0
END DESCRIPTION:
XS GIS Cut Line= 3
      1991074.98       13941875.        1990925.       13941875.
      1990825.08       13941875.
#Sta/Elev= 30
  4854.6  1924.7  4858.8 1923.93  4861.8 1922.79  4882.5 1918.58  4885.5 1917.08
  4912.8 1909.51  4926.9 1904.44  4942.5 1898.64  4957.5 1891.95  4963.8 1889.72
  4975.5 1886.83  5002.5 1881.09  5005.8 1879.17  5006.8  1876.5  5007.1    1876
  5010.6    1876  5010.8  1876.5  5020.5  1877.6  5029.5 1886.72  5032.5 1889.12
  5047.5 1895.45  5053.8 1898.72  5062.5 1904.04  5071.8  1908.9  5080.8 1914.52
  5086.5 1918.79  5092.5 1922.07  5095.5 1923.43  5101.5 1924.24  5104.5 1925.33
#Mann= 4 ,-1 , 0
  4854.6      .1       0  4926.9     .07       0  5006.8     .05       0
  5010.8     .07       0
Bank Sta=5006.8,5010.8
XS Rating Curve= 0 ,0
Exp/Cntr=0.3,0.1

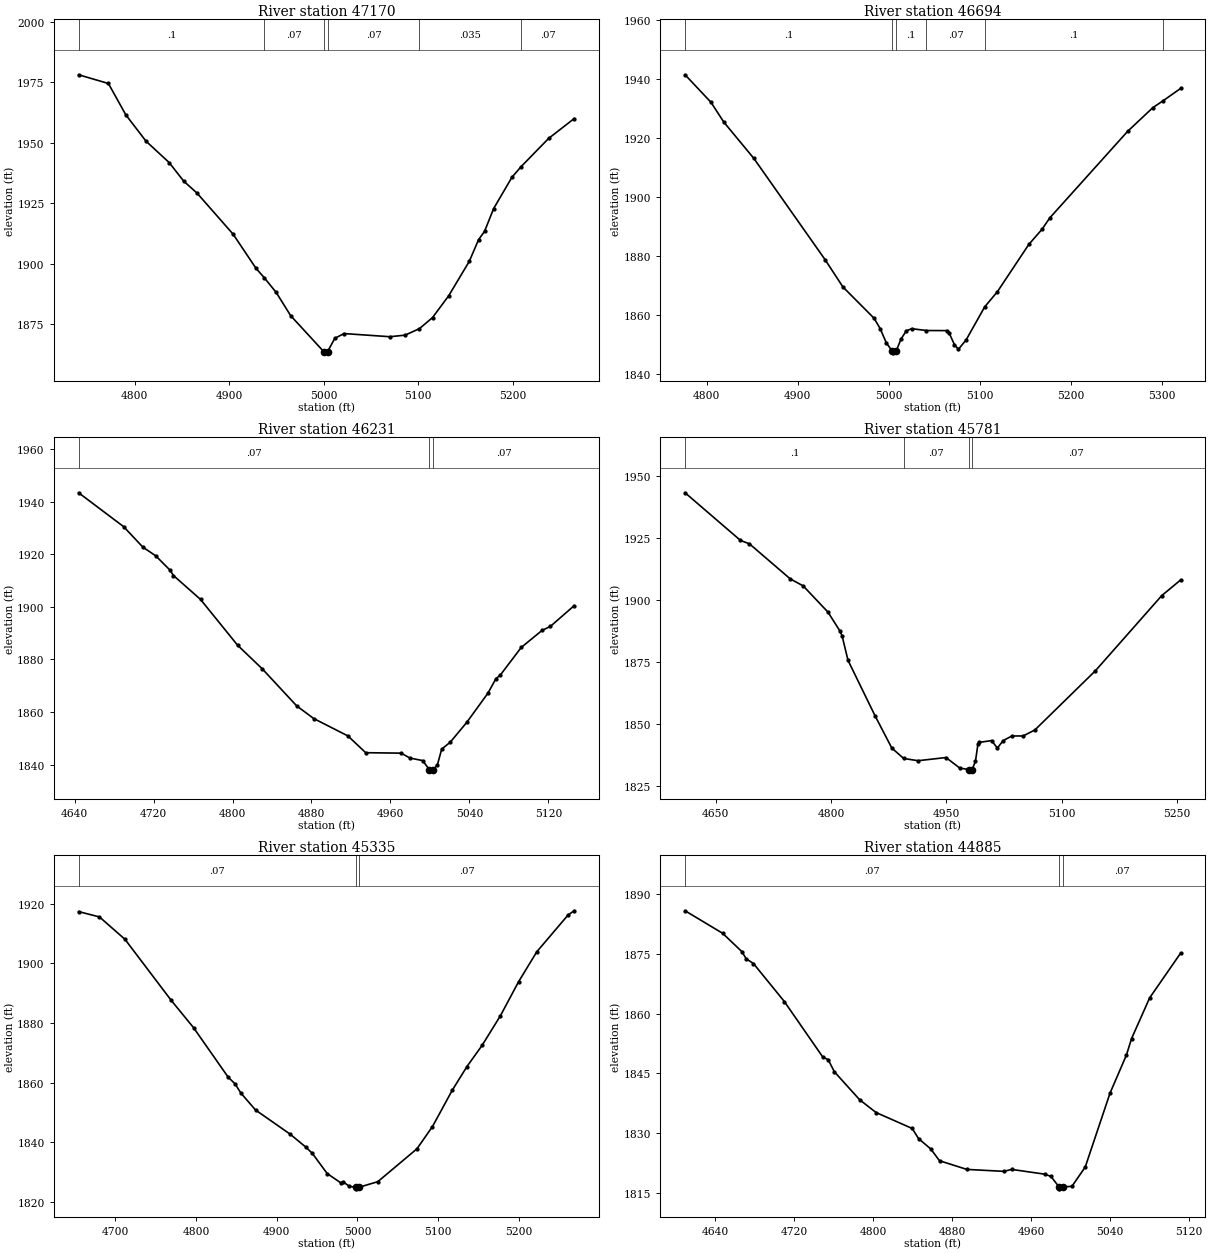
Type RM Length L Ch R = 1 ,47170   ,476,476,476
BEGIN DESCRIPTION:
North Creek 96.0
END DESCRIPTION:
XS GIS Cut Line= 3
      1991074.96     13941375.01        1990825.       13941425.
      1990574.97     13941525.01
#Sta/Elev= 30
  4740.8 1978.01  4772.3 1974.41  4790.7 1961.47  4812.1 1950.58  4836.6 1941.74
  4851.9  1934.1    4866 1929.16  4904.3 1912.13  4928.4 1898.08    4937 1894.26
  4949.8  1888.1  4965.1 1878.51  5000.1 1863.66  5000.4 1863.16  5004.1 1863.66
  5011.8 1869.15  5021.5 1871.12    5070 1869.82  5086.1 1870.46  5101.3 1873.15
  5115.2 1877.74  5132.3 1886.76    5154 1900.92  5163.9 1909.92  5170.2 1913.33
  5179.8 1922.74  5199.2  1935.7  5208.9 1940.08    5238 1951.73    5265 1959.92
#Mann= 6 ,-1 , 0
  4740.8      .1       0    4937     .07       0  5000.1     .05       0
  5004.1     .07       0  5101.3    .035       0  5208.9     .07       0
Bank Sta=5000.1,5004.1
XS Rating Curve= 0 ,0
Exp/Cntr=0.3,0.1

Type RM Length L Ch R = 1 ,46694   ,463,463,463
BEGIN DESCRIPTION:
North Creek 95.0
END DESCRIPTION:
XS GIS Cut Line= 3
        1991025.       13941125.        1990825.       13941025.
      1990574.97     13940824.98
#Sta/Elev= 30
  4776.5 1941.39    4805 1932.04  4818.9 1925.39    4852 1913.04  4930.2 1878.73
  4949.7 1869.51  4983.9 1858.91  4990.6  1855.4  4997.3 1850.58    5004  1847.7
  5004.2  1847.2    5008  1847.7  5013.4 1851.85  5019.3 1854.68  5025.2 1855.38
  5041.3 1854.76  5063.6 1854.73  5066.2 1853.95  5072.1 1849.95  5076.4 1848.39
  5084.9 1851.58  5105.3 1862.79  5119.2  1867.9  5153.7 1883.93  5168.2 1889.05
  5176.7 1892.91  5262.1 1922.22  5289.8 1930.26  5300.5 1932.47  5320.3 1936.77
#Mann= 6 ,-1 , 0
  4776.5      .1       0    5004     .05       0    5008      .1       0
  5041.3     .07       0  5105.3      .1       0  5300.5     .07       0
Bank Sta=5004,5008
XS Rating Curve= 0 ,0
Exp/Cntr=0.3,0.1

Type RM Length L Ch R = 1 ,46231   ,450,450,450
BEGIN DESCRIPTION:
North Creek 94.0
END DESCRIPTION:
XS GIS Cut Line= 3
      1991175.02     13940775.01        1990875.       13940575.
        1990775.       13940475.
#Sta/Elev= 30
  4644.1 1943.36  4689.7 1930.47  4709.2 1922.67  4722.2 1919.39  4736.6 1913.96
  4740.2 1911.88  4767.6 1902.79  4805.1 1885.39  4830.3 1876.33    4865  1862.3
  4882.3 1857.48  4916.9 1850.88  4934.9  1844.5  4970.9 1844.33  4979.6 1842.48
  4992.6  1841.5  4999.3  1838.1  4999.5  1837.6  5003.3  1838.1  5007.5 1839.82
  5011.9 1845.88  5020.6  1848.5  5037.4 1856.09  5058.8 1867.17  5066.8 1872.63
  5071.3 1874.04  5092.5 1884.54  5113.5 1890.99    5122 1892.54  5146.1 1900.42
#Mann= 3 ,-1 , 0
  4644.1     .07       0  4999.3     .05       0  5003.3     .07       0
Bank Sta=4999.3,5003.3
XS Rating Curve= 0 ,0
Exp/Cntr=0.3,0.1

Type RM Length L Ch R = 1 ,45781   ,446,446,446
BEGIN DESCRIPTION:
North Creek 93.0
END DESCRIPTION:
XS GIS Cut Line= 3
      1991429.69     13940475.45        1991125.       13940225.
      1990975.07     13940025.09
#Sta/Elev= 30
  4610.2 1943.28  4682.2 1924.06  4693.9 1922.67  4746.9 1908.54  4763.8 1905.69
  4795.9 1895.14  4811.4 1887.57  4814.3 1885.57    4822 1875.68    4857 1853.39
    4879 1840.25  4894.4 1836.06  4913.1 1835.16  4949.4 1836.44  4967.3  1832.2
  4979.3 1831.57  4979.5 1831.07  4983.3 1831.57  4987.7 1834.86  4990.9 1841.75
    4992 1842.52  5008.7 1843.28  5016.2 1840.26  5023.7 1843.26    5035 1845.13
  5049.8 1845.15    5065 1847.57  5143.7 1871.46    5230  1901.8  5254.5  1908.1
#Mann= 4 ,-1 , 0
  4610.2      .1       0  4894.4     .07       0  4979.3     .05       0
  4983.3     .07       0
Bank Sta=4979.3,4983.3
XS Rating Curve= 0 ,0
Exp/Cntr=0.3,0.1

Type RM Length L Ch R = 1 ,45335   ,450,450,450
BEGIN DESCRIPTION:
North Creek 92.0
END DESCRIPTION:
XS GIS Cut Line= 3
      1991612.23     13939997.73        1991275.       13939925.
      1991025.04     13939825.02
#Sta/Elev= 30
  4654.5 1917.32  4680.3 1915.52  4711.9 1908.03  4769.3 1887.53  4796.9  1878.4
  4839.9 1861.77  4848.2  1859.6  4855.8 1856.39  4873.8 1850.77  4916.6 1842.69
  4936.6 1838.22  4944.2 1836.22  4962.6 1829.46  4979.5 1826.34    4982 1826.71
  4990.2 1825.19  4997.7 1824.84  4997.9 1824.34  5001.7 1824.84  5025.3 1826.74
  5073.8 1837.76  5093.1 1845.24  5117.4 1857.32  5135.8 1865.35  5154.5 1872.42
  5177.2 1882.35  5199.8  1893.8  5222.4 1903.85  5261.2 1916.19  5268.7 1917.59
#Mann= 3 ,-1 , 0
  4654.5     .07       0  4997.7     .05       0  5001.7     .07       0
Bank Sta=4997.7,5001.7
XS Rating Curve= 0 ,0
Exp/Cntr=0.3,0.1

Type RM Length L Ch R = 1 ,44885   ,468,468,468
BEGIN DESCRIPTION:
North Creek 91.0
END DESCRIPTION:
XS GIS Cut Line= 3
      1991674.97     13939824.96        1991425.       13939525.
      1991324.97     13939474.99
#Sta/Elev= 30
  4609.3 1885.77  4647.4 1880.12  4666.9 1875.52  4671.2 1873.74  4678.6 1872.55
  4709.9 1863.03  4748.9 1849.11  4754.3 1848.48  4760.6 1845.43  4786.2 1838.42
  4802.9 1835.21  4839.5 1831.22  4845.9  1828.7  4858.3 1826.08  4867.2 1823.13
  4894.9 1820.96  4932.5 1820.47  4940.3 1820.96  4973.7 1819.77  4980.1 1819.21
  4988.3 1816.59  4988.6 1816.09  4992.3 1816.59  5001.4 1816.71  5014.9 1821.56
    5040 1840.06  5056.7 1849.65  5061.8 1853.72  5080.2 1863.95  5111.6 1875.16
#Mann= 3 ,-1 , 0
  4609.3     .07       0  4988.3     .05       0  4992.3     .07       0
Bank Sta=4988.3,4992.3
XS Rating Curve= 0 ,0
Exp/Cntr=0.3,0.1

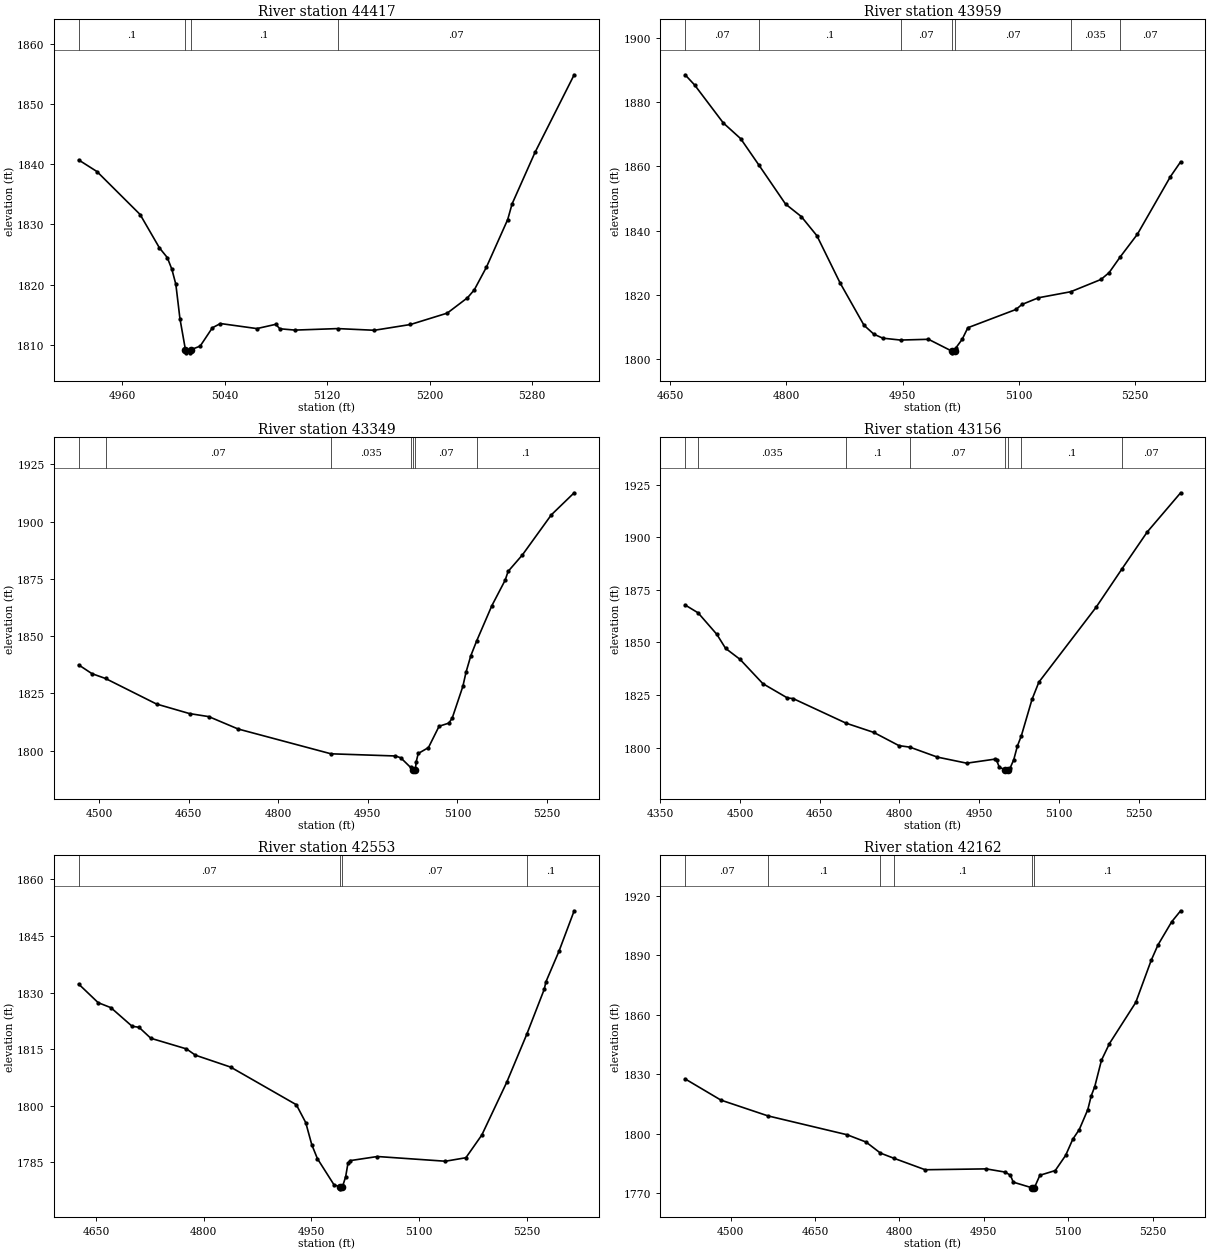
Type RM Length L Ch R = 1 ,44417   ,458,458,458
BEGIN DESCRIPTION:
North Creek 90.0
END DESCRIPTION:
XS GIS Cut Line= 3
        1991825.       13939275.        1991775.       13939225.
      1991475.04     13939125.01
#Sta/Elev= 30
  4925.9 1840.72  4940.2 1838.79  4973.9 1831.65    4989  1826.1  4995.1  1824.5
  4998.7 1822.55  5001.8 1820.05    5005 1814.34  5009.3 1809.16  5009.6 1808.66
  5013.1 1808.66  5013.3 1809.16  5020.8 1809.78  5030.3 1812.82  5036.6 1813.53
  5065.1 1812.69  5079.8  1813.4    5083 1812.66  5094.8 1812.44  5128.2 1812.69
  5156.8 1812.41    5185 1813.37  5213.7 1815.26  5229.5 1817.81  5234.8 1819.12
  5244.3  1822.9  5260.9 1830.81  5264.3  1833.4  5282.2 1841.96  5312.8 1854.87
#Mann= 4 ,-1 , 0
  4925.9      .1       0  5009.3     .05       0  5013.3      .1       0
  5128.2     .07       0
Bank Sta=5009.3,5013.3
XS Rating Curve= 0 ,0
Exp/Cntr=0.3,0.1

Type RM Length L Ch R = 1 ,43959   ,610,610,610
BEGIN DESCRIPTION:
North Creek 89.0
END DESCRIPTION:
XS GIS Cut Line= 3
      1992074.96     13938974.98        1991775.       13938825.
      1991475.01       13938875.
#Sta/Elev= 30
  4669.2 1888.55  4681.4  1885.4  4718.5 1873.55  4740.9 1868.66  4764.4 1860.45
  4798.8  1848.3  4819.2 1844.39  4839.3 1838.43  4869.2 1823.74  4900.1 1810.54
  4912.8 1807.77  4924.3 1806.53  4947.2 1805.94  4983.3 1806.18  5013.7 1802.46
  5013.9 1801.96  5017.7 1802.46  5018.7 1803.51  5026.8 1806.19  5034.1 1809.78
  5096.1 1815.46  5103.9 1817.02  5125.2 1819.11  5166.9 1820.99  5205.9 1824.81
  5216.4 1826.94  5230.5 1831.76  5252.9  1838.9  5295.5 1856.83  5308.7 1861.45
#Mann= 7 ,-1 , 0
  4669.2     .07       0  4764.4      .1       0  4947.2     .07       0
  5013.7     .05       0  5017.7     .07       0  5166.9    .035       0
  5230.5     .07       0
Bank Sta=5013.7,5017.7
XS Rating Curve= 0 ,0
Exp/Cntr=0.3,0.1

Type RM Length L Ch R = 1 ,43349   ,193,193,193
BEGIN DESCRIPTION:
North Creek 88.0
END DESCRIPTION:
XS GIS Cut Line= 3
        1992075.       13938675.      1991759.04     13938280.08
      1991474.98     13938124.99
#Sta/Elev= 30
    4466 1837.43  4488.3 1833.59    4511 1831.48  4596.4 1820.32  4651.6 1816.15
  4683.9 1814.82    4733 1809.41  4888.4 1798.58  4996.3 1797.63  5005.2 1796.83
  5021.5 1792.66  5025.6 1791.64  5025.8 1791.14  5029.6 1791.64    5031 1795.09
  5034.4 1798.72  5051.5  1801.3  5069.3 1810.62  5085.7 1811.99  5091.4 1814.27
  5109.1 1828.04  5114.4 1834.24  5122.4 1841.41    5132 1847.77  5157.7 1863.32
  5179.9 1874.43  5184.8 1878.25  5208.7 1885.44  5257.2 1902.97  5295.4  1912.6
#Mann= 7 ,-1 , 0
    4466      .1       0    4511     .07       0  4888.4    .035       0
  5021.5     .07       0  5025.6    .035       0  5029.6     .07       0
    5132      .1       0
Bank Sta=5025.6,5029.6
XS Rating Curve= 0 ,0
Exp/Cntr=0.3,0.1

Type RM Length L Ch R = 1 ,43156   ,603,603,603
BEGIN DESCRIPTION:
North Creek 87.0
END DESCRIPTION:
XS GIS Cut Line= 3
      1992326.37     13938575.76      1991884.46     13938157.56
      1991725.03     13937875.06
#Sta/Elev= 30
  4396.5 1867.83    4421 1864.08  4456.2 1853.88  4472.7  1847.2    4500 1841.96
  4542.9 1830.42  4589.2 1823.61  4599.8 1823.34  4699.6 1811.63  4751.6 1807.25
    4799 1800.97  4819.8 1800.23  4871.4 1795.51  4926.6 1792.62  4979.6 1794.54
  4982.9 1793.92  4988.1 1790.63  4999.4 1789.48  4999.6 1788.98  5003.4 1789.48
  5008.2 1790.28  5015.1 1794.21    5022 1800.76  5029.4  1805.6  5049.5 1822.92
  5062.4 1831.13  5170.3 1866.79  5218.2 1884.73  5266.5 1902.56  5329.3 1921.16
#Mann= 8 ,-1 , 0
  4396.5     .07       0    4421    .035       0  4699.6      .1       0
  4819.8     .07       0  4999.4     .05       0  5003.4     .07       0
  5029.4      .1       0  5218.2     .07       0
Bank Sta=4999.4,5003.4
XS Rating Curve= 0 ,0
Exp/Cntr=0.3,0.1

Type RM Length L Ch R = 1 ,42553   ,391,391,391
BEGIN DESCRIPTION:
North Creek 86.0
END DESCRIPTION:
XS GIS Cut Line= 3
      1992618.27     13938074.28        1992275.       13937925.
      1991974.96     13937824.99
#Sta/Elev= 30
  4625.7 1832.28  4652.9 1827.34  4670.7 1826.01  4700.1  1821.1  4709.9  1820.8
  4726.3  1817.9    4776 1815.08  4788.4 1813.42  4837.5 1810.26  4929.1 1800.28
  4942.2 1795.54  4950.6 1789.69  4958.5 1785.97  4981.4 1779.11  4989.3 1778.48
  4989.5 1777.98  4993.3 1778.48  4997.8 1781.16    5001 1784.71  5004.1 1785.46
  5042.1 1786.55  5136.9  1785.3  5165.4 1786.23  5187.6 1792.25  5222.3 1806.23
  5250.2 1818.94  5274.6 1830.89  5276.9 1832.85  5295.1 1840.96  5316.3  1851.7
#Mann= 4 ,-1 , 0
  4625.7     .07       0  4989.3     .05       0  4993.3     .07       0
  5250.2      .1       0
Bank Sta=4989.3,4993.3
XS Rating Curve= 0 ,0
Exp/Cntr=0.3,0.1

Type RM Length L Ch R = 1 ,42162   ,515,515,515
BEGIN DESCRIPTION:
North Creek 85.0
END DESCRIPTION:
XS GIS Cut Line= 3
      1992642.86     13938022.43      1992272.22     13937555.96
        1992225.       13937275.
#Sta/Elev= 30
    4419 1827.62  4482.7 1816.91  4566.3 1808.95  4706.9 1799.44  4740.5 1795.77
  4766.2 1790.18  4789.9  1787.6  4845.7 1781.78    4954 1782.22  4987.8  1780.6
  4997.2 1778.99  5002.2 1775.53  5035.7 1772.65    5036 1772.15  5039.7 1772.65
  5049.5 1778.99  5076.8 1781.37  5095.3 1789.02  5108.1 1797.23  5119.5 1802.02
  5134.7 1812.12  5140.8 1819.08  5147.1 1823.76    5159 1837.03  5173.2 1845.45
  5219.9 1866.17  5247.3 1887.38  5259.4 1895.18  5283.8 1906.88  5299.7 1912.43
#Mann= 6 ,-1 , 0
    4419     .07       0  4566.3      .1       0  4766.2     .07       0
  4789.9      .1       0  5035.7     .05       0  5039.7      .1       0
Bank Sta=5035.7,5039.7
XS Rating Curve= 0 ,0
Exp/Cntr=0.3,0.1

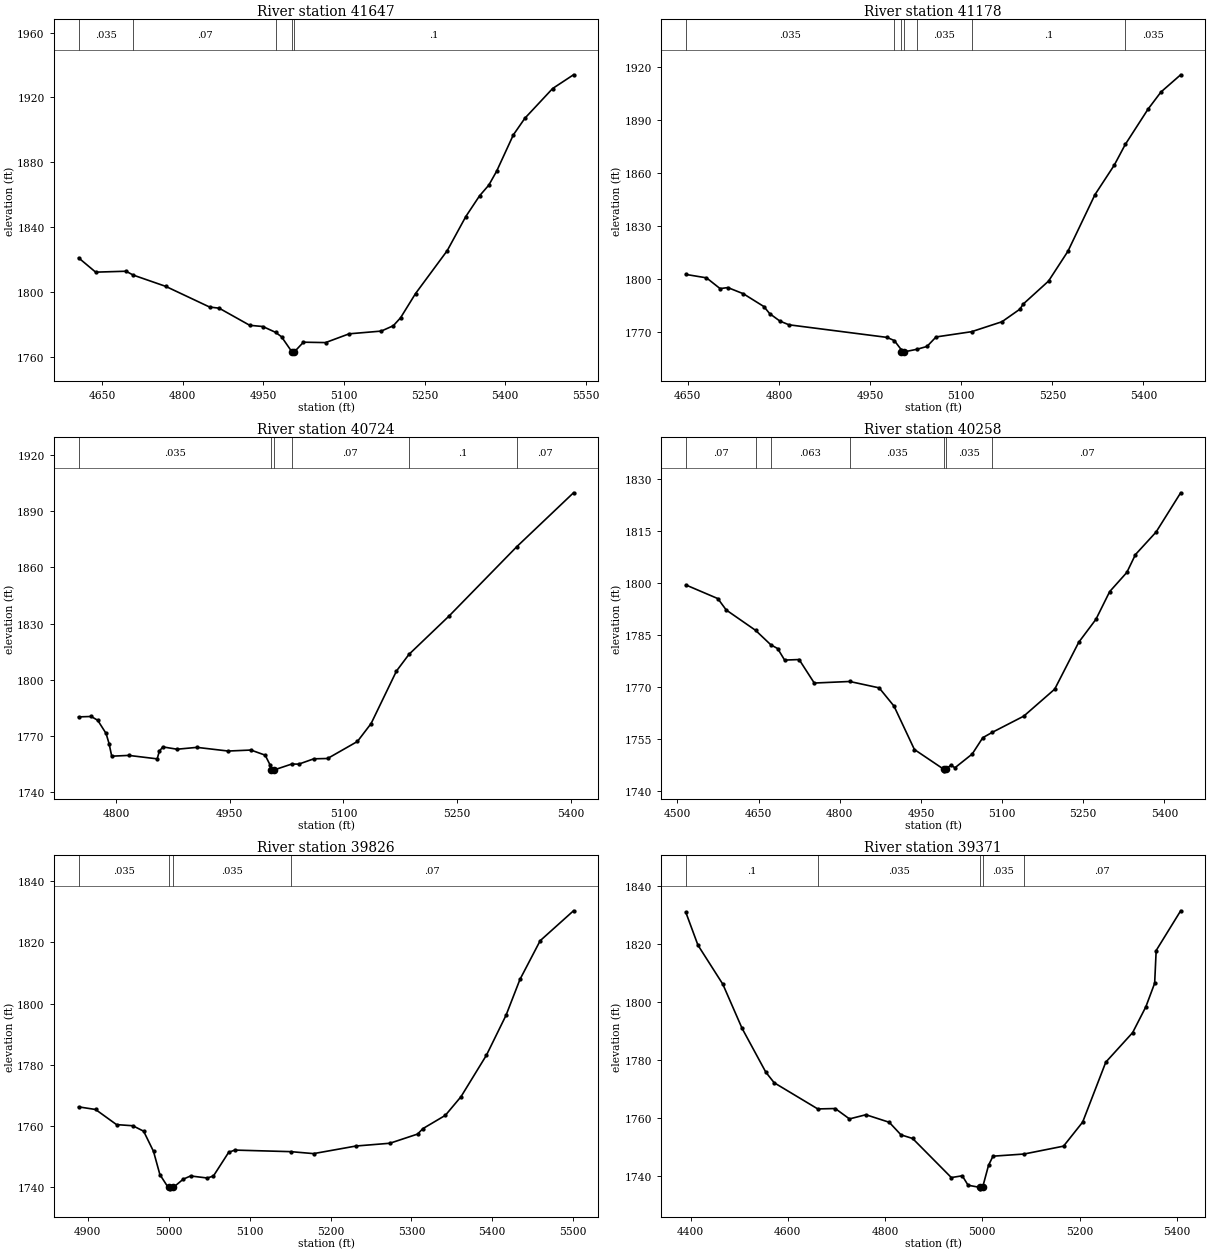
Type RM Length L Ch R = 1 ,41647   ,469,469,469
BEGIN DESCRIPTION:
North Creek 84.0
END DESCRIPTION:
XS GIS Cut Line= 3
       1992882.9     13937853.58        1992675.       13937525.
      1992275.03     13937175.03
#Sta/Elev= 30
  4606.7 1821.07  4638.4 1812.26  4694.9 1812.82  4708.4 1810.43  4768.7 1803.49
  4850.3 1790.74  4868.1 1790.03  4924.9 1779.48  4949.3 1778.73  4973.1 1775.12
  4984.1 1772.38  5003.6    1763  5003.9  1762.5  5007.6    1763  5024.8 1769.06
  5065.9 1768.82  5109.8 1774.23  5169.5 1775.91  5191.9 1779.21  5205.4 1784.11
  5233.3 1799.08  5292.1 1825.48  5326.7 1846.52  5352.2 1859.28  5369.5 1865.92
  5384.1 1874.53  5415.1 1896.89  5436.6 1907.17  5488.2 1925.49    5527 1933.96
#Mann= 5 ,-1 , 0
  4606.7    .035       0  4708.4     .07       0  4973.1      .1       0
  5003.6     .05       0  5007.6      .1       0
Bank Sta=5003.6,5007.6
XS Rating Curve= 0 ,0
Exp/Cntr=0.3,0.1

Type RM Length L Ch R = 1 ,41178   ,454,454,454
BEGIN DESCRIPTION:
North Creek 83.0
END DESCRIPTION:
XS GIS Cut Line= 3
        1993175.       13937425.        1992925.       13937175.
      1992575.02     13936875.02
#Sta/Elev= 30
  4646.7 1802.46  4680.8 1800.51  4703.2  1794.4  4715.9 1794.99  4741.4 1791.49
  4775.3  1784.2  4784.8 1780.19  4801.7 1775.94  4816.6 1773.84  4977.8  1766.7
    4990 1764.88  5001.1 1759.81  5001.3 1758.42  5001.5 1757.92  5005.3 1758.42
  5027.3 1759.95  5043.7 1761.55  5058.6 1766.94  5117.1 1769.93  5167.1 1775.58
  5196.9 1782.79  5201.7 1785.51  5243.7 1798.66  5275.6 1815.59  5320.2 1847.79
  5351.9 1864.51    5370 1876.25  5407.5 1896.33  5428.8 1906.07  5461.2 1915.84
#Mann= 7 ,-1 , 0
  4646.7    .035       0    4990     .07       0  5001.3     .05       0
  5005.3     .07       0  5027.3    .035       0  5117.1      .1       0
    5370    .035       0
Bank Sta=5001.3,5005.3
XS Rating Curve= 0 ,0
Exp/Cntr=0.3,0.1

Type RM Length L Ch R = 1 ,40724   ,466,466,466
BEGIN DESCRIPTION:
North Creek 82.0
END DESCRIPTION:
XS GIS Cut Line= 3
        1993275.       13936925.        1993075.       13936775.
      1992675.01       13936725.
#Sta/Elev= 30
  4750.5  1780.1  4767.1 1780.32  4775.7 1778.29  4786.7 1771.29  4790.7 1765.86
  4794.2  1759.1  4816.7 1759.52  4854.2 1757.67  4857.1 1761.82  4861.7 1764.06
  4880.4 1762.82  4906.7 1763.81  4947.9 1761.85  4977.9 1762.38  4996.7 1759.65
  5003.4 1754.23  5004.5 1751.77  5004.8 1751.27  5008.6 1751.77  5031.9 1754.92
    5041 1754.85  5060.9 1757.69  5079.1 1757.87  5118.4 1766.95  5136.5 1776.54
    5170 1804.62  5186.5 1813.52  5239.3 1833.97  5328.8 1871.07  5403.6 1899.86
#Mann= 6 ,-1 , 0
  4750.5    .035       0  5004.5    .035       0  5008.6    .035       0
  5031.9     .07       0  5186.5      .1       0  5328.8     .07       0
Bank Sta=5004.5,5008.6
XS Rating Curve= 0 ,0
Exp/Cntr=0.3,0.1

Type RM Length L Ch R = 1 ,40258   ,432,432,432
BEGIN DESCRIPTION:
North Creek 81.0
END DESCRIPTION:
XS GIS Cut Line= 4
      1993654.92     13936662.54        1993225.       13936425.
      1993170.59     13936405.36      1992825.04     13936524.99
#Sta/Elev= 30
  4515.3 1799.52  4574.6 1795.57  4590.1 1792.28  4644.2 1786.43  4672.5 1782.24
  4685.1 1781.16    4698 1777.83  4724.8 1777.99  4752.8 1771.21  4818.3 1771.66
  4872.7 1769.82  4900.2 1764.55  4937.9 1752.03  4991.7 1746.38  4992.1 1745.88
  4996.7 1746.38  5005.2 1747.54  5012.8 1746.77  5044.7 1750.73  5064.3 1755.45
  5082.2 1757.02    5140 1761.66  5197.2 1769.45  5241.6 1782.97  5273.4  1789.6
  5298.8 1797.59  5330.5 1803.12  5346.4 1808.27  5384.5 1814.76    5430  1826.1
#Mann= 7 ,-1 , 0
  4515.3     .07       0  4644.2    .035       0  4672.5    .063       0
  4818.3    .035       0  4991.7    .035       0  4996.7    .035       0
  5082.2     .07       0
Bank Sta=4991.7,4996.7
XS Rating Curve= 0 ,0
Exp/Cntr=0.3,0.1

Type RM Length L Ch R = 1 ,39826   ,455,455,455
BEGIN DESCRIPTION:
North Creek 80.0
END DESCRIPTION:
XS GIS Cut Line= 3
      1993524.96     13936124.98        1993425.       13936075.
      1993024.97     13935774.98
#Sta/Elev= 30
  4888.6 1766.29  4909.6 1765.43  4935.5  1760.5  4955.6 1760.13    4969 1758.35
  4981.2 1751.77  4989.1 1744.19  4999.2 1740.06  5000.8 1740.05  5001.2 1739.55
  5005.9 1740.05  5017.8 1742.68    5027 1743.75  5047.8 1743.08  5055.3 1743.75
  5074.1 1751.45  5081.6 1752.19    5151 1751.68  5179.1 1751.04  5231.6 1753.52
  5273.4 1754.42  5307.7 1757.42  5314.1 1759.17    5342 1763.53  5361.3  1769.6
  5392.8 1783.16    5417 1796.17  5434.2 1807.86  5459.2 1820.49  5500.4 1830.25
#Mann= 4 ,-1 , 0
  4888.6    .035       0  5000.8    .035       0  5005.9    .035       0
    5151     .07       0
Bank Sta=5000.8,5005.9
XS Rating Curve= 0 ,0
Exp/Cntr=0.3,0.1

Type RM Length L Ch R = 1 ,39371   ,431,431,431
BEGIN DESCRIPTION:
North Creek 79.0
END DESCRIPTION:
XS GIS Cut Line= 3
      1994039.12     13935703.72        1993425.       13935675.
        1993025.       13935725.
#Sta/Elev= 30
  4390.1  1830.9  4415.2 1819.51  4466.3 1806.07  4505.9 1790.85  4554.7 1775.75
  4571.9 1772.09  4661.6 1763.06  4697.5  1763.2  4726.8 1759.62  4760.6 1761.06
  4808.6 1758.46  4832.7 1754.13  4856.7 1752.87  4936.3  1739.4  4958.8 1740.01
  4970.8 1736.75  4995.1 1736.01  4995.5 1735.51  5000.6 1736.01  5012.9 1743.67
    5022 1746.77  5085.8 1747.51  5167.1 1750.23  5206.4 1758.52    5254 1779.19
  5309.2 1789.37  5336.4 1798.28  5354.5  1806.4  5357.6 1817.68    5408 1831.38
#Mann= 5 ,-1 , 0
  4390.1      .1       0  4661.6    .035       0  4995.1    .035       0
  5000.6    .035       0  5085.8     .07       0
Bank Sta=4995.1,5000.6
XS Rating Curve= 0 ,0
Exp/Cntr=0.3,0.1