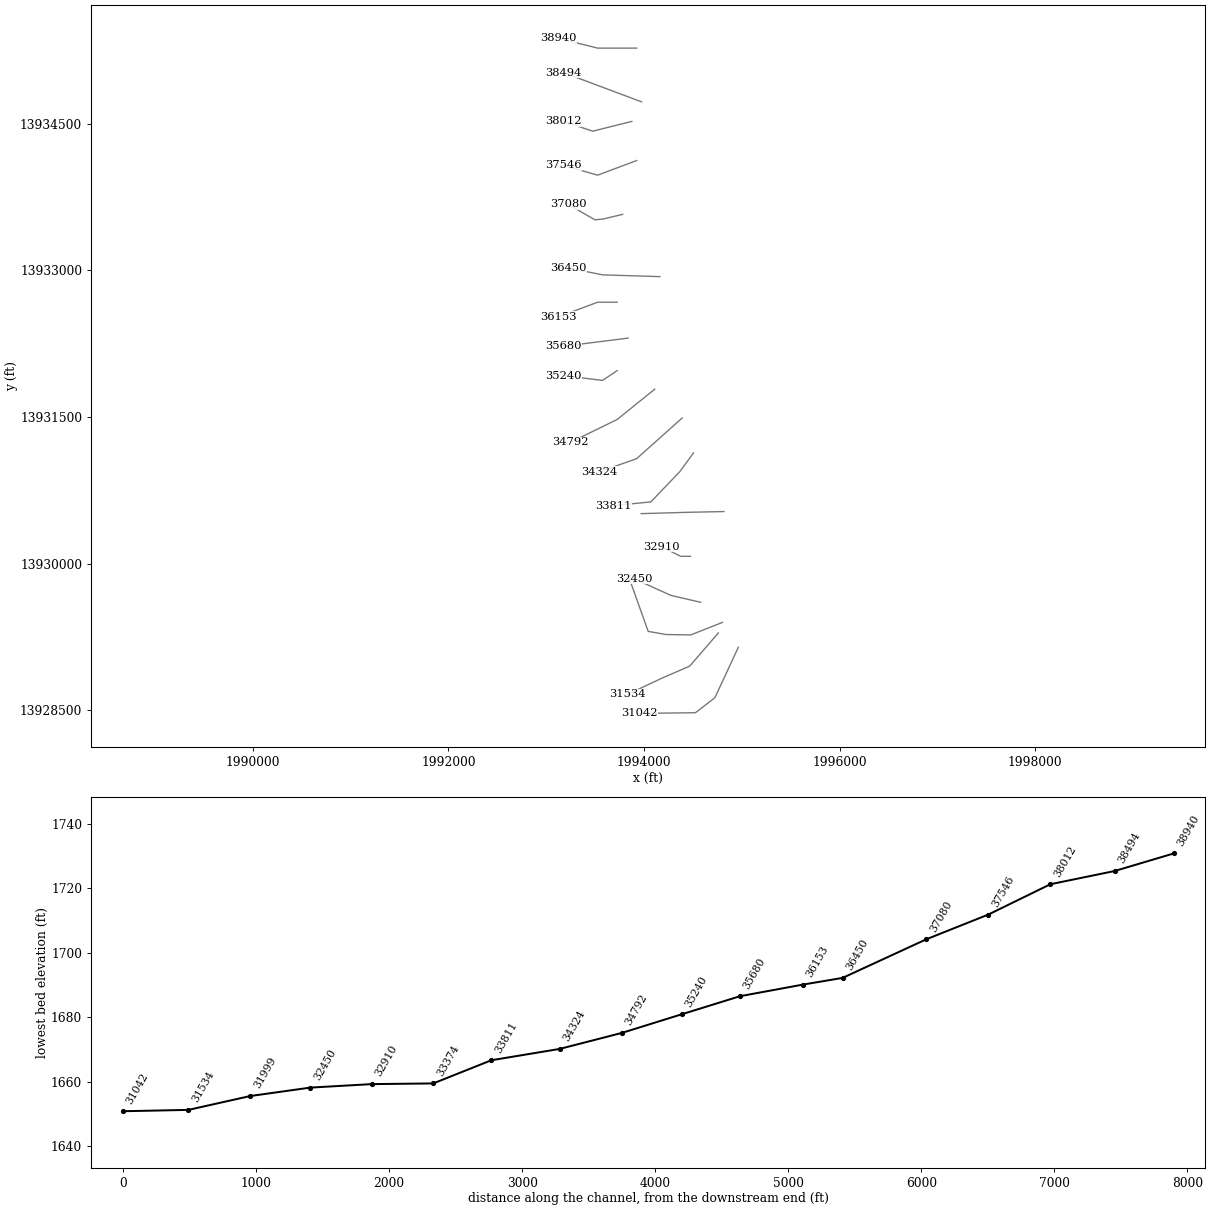
HEC-RAS study North Creek.prj: North Creek Base Level Engineering

--- North Creek.g01 (geometry) --- (continued)

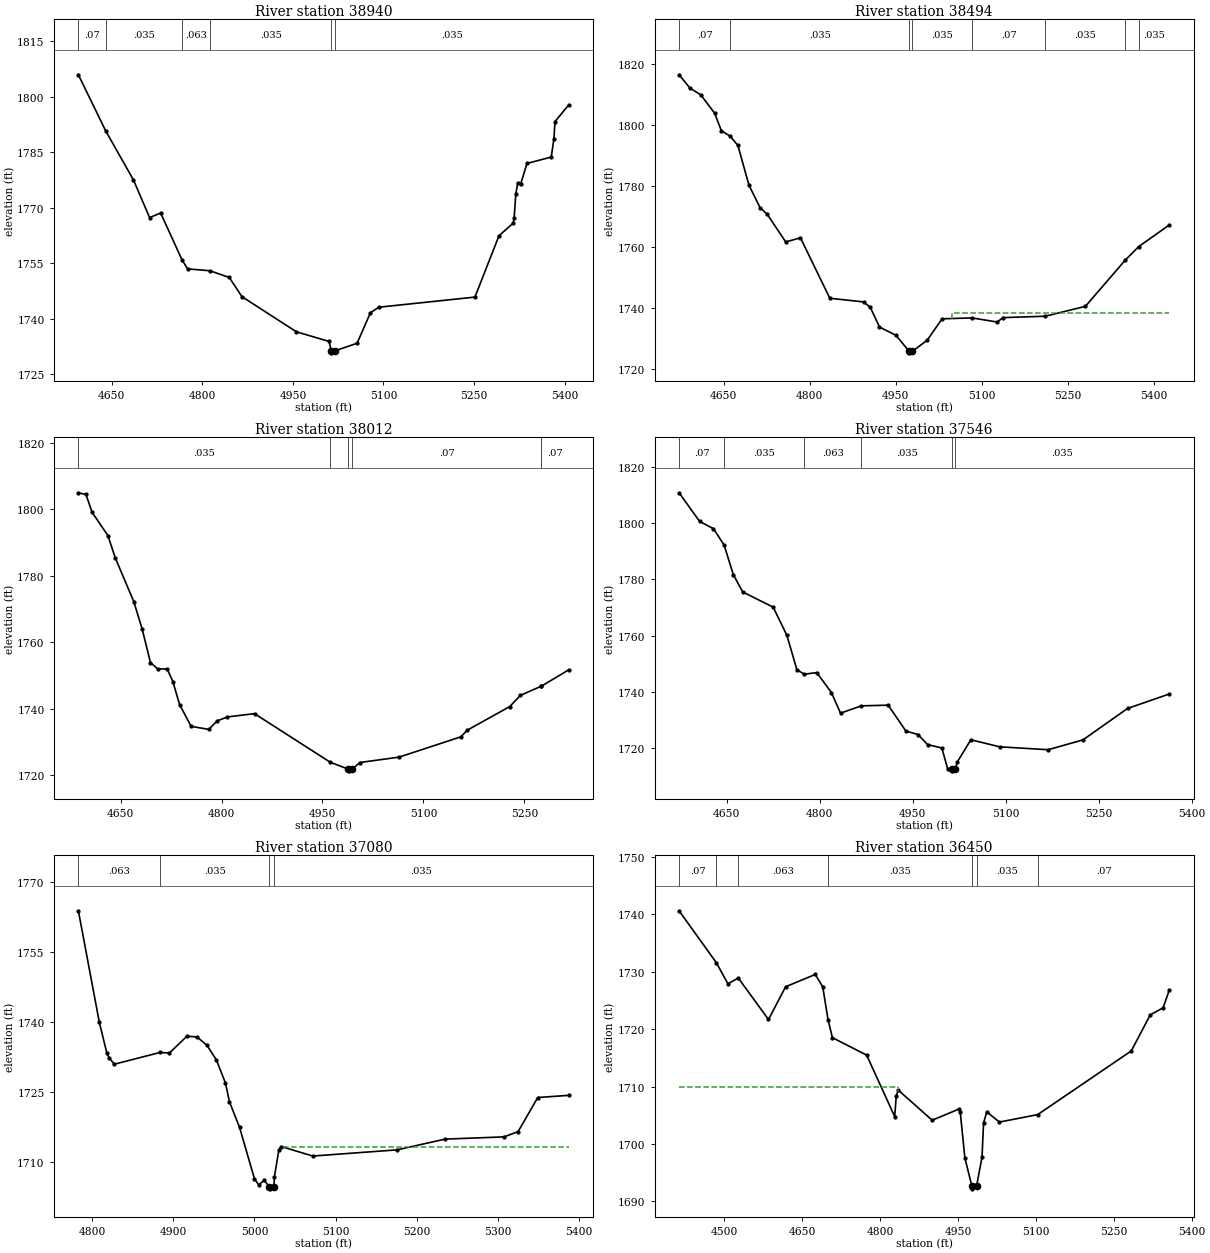
Type RM Length L Ch R = 1 ,38940   ,446,446,446
BEGIN DESCRIPTION:
North Creek 78.0
END DESCRIPTION:
XS GIS Cut Line= 3
      1993925.01       13935275.        1993525.       13935275.
      1993125.02       13935375.
#Sta/Elev= 30
  4594.6 1805.89    4640  1790.7  4685.9 1777.49  4712.6 1767.33  4730.9 1768.56
  4766.2 1755.96  4775.6 1753.49  4812.6 1752.98  4844.6 1751.17  4865.6 1745.99
  4955.9 1736.49    5010  1733.9  5013.5 1731.32  5013.9 1730.82    5019 1731.32
  5056.4 1733.41  5078.4 1741.64  5092.4 1743.14  5251.6 1745.87  5291.4 1762.42
    5315 1765.85  5316.6 1767.31  5319.3  1773.7  5322.4 1776.56  5327.4 1776.41
  5337.8 1781.96    5378 1783.67  5382.5 1788.68  5384.2 1793.25  5406.9 1797.74
#Mann= 6 ,-1 , 0
  4594.6     .07       0    4640    .035       0  4766.2    .063       0
  4812.6    .035       0  5013.5    .035       0    5019    .035       0
Bank Sta=5013.5,5019
XS Rating Curve= 0 ,0
Exp/Cntr=0.3,0.1

Type RM Length L Ch R = 1 ,38494   ,482,482,482
BEGIN DESCRIPTION:
North Creek 77.0
END DESCRIPTION:
XS GIS Cut Line= 3
      1993975.03     13934724.99        1993575.       13934875.
      1993175.03     13935024.99
#Sta/Elev= 30
  4572.4 1816.51  4591.5 1812.13  4610.2 1809.92  4634.3 1803.93  4646.1 1798.19
  4661.6 1796.35  4674.9 1793.33  4694.2 1780.29  4713.4 1772.99  4726.2 1770.72
  4758.2 1761.71  4783.9 1763.06  4835.1 1743.24  4894.1 1742.04  4905.6 1740.26
  4921.6 1733.82  4950.4 1731.08  4973.3 1725.85  4973.8 1725.35  4978.9 1725.85
  5004.9 1729.51  5030.6  1736.5    5083  1736.8  5126.7 1735.45  5136.9  1736.9
  5210.5 1737.35  5280.5  1740.6  5349.9 1755.75  5373.5  1760.2  5426.8 1767.29
#Mann= 8 ,-1 , 0
  4572.4     .07       0  4661.6    .035       0  4973.3    .035       0
  4978.9    .035       0    5083     .07       0  5210.5    .035       0
  5349.9     .07       0  5373.5    .035       0
#XS Ineff= 2 , 0
                         5047.35         1738.56
Permanent Ineff=
       F       F
Bank Sta=4973.3,4978.9
XS Rating Curve= 0 ,0
Exp/Cntr=0.3,0.1

Type RM Length L Ch R = 1 ,38012   ,466,466,466
BEGIN DESCRIPTION:
North Creek 76.0
END DESCRIPTION:
XS GIS Cut Line= 3
      1993874.96     13934524.99        1993475.       13934425.
        1993175.       13934525.
#Sta/Elev= 30
  4587.3 1805.03  4598.6 1804.52  4607.8  1799.1  4631.2 1792.15  4641.9 1785.53
  4669.7 1772.21  4682.1 1763.96  4694.4 1753.89    4705 1751.98  4719.2 1751.96
  4727.7 1748.17  4737.7 1741.21  4754.9 1734.66    4781 1733.75  4793.4 1736.29
  4808.8 1737.51    4849 1738.49  4961.7 1723.83  4988.4 1721.76  4988.9 1721.26
  4994.1 1721.76  5005.6 1723.77  5063.8 1725.39  5155.5  1731.5    5165 1733.49
  5228.3 1740.63  5244.1 1744.01  5274.7 1746.72  5275.2 1746.76  5315.8 1751.68
#Mann= 6 ,-1 , 0
  4587.3    .035       0  4961.7     .07       0  4988.4     .05       0
  4994.1     .07       0  5274.7    .035       0  5275.2     .07       0
Bank Sta=4988.4,4994.1
XS Rating Curve= 0 ,0
Exp/Cntr=0.3,0.1

Type RM Length L Ch R = 1 ,37546   ,466,466,466
BEGIN DESCRIPTION:
North Creek 75.0
END DESCRIPTION:
XS GIS Cut Line= 3
        1993925.       13934125.        1993525.       13933975.
        1993175.       13934075.
#Sta/Elev= 30
  4572.9 1810.81    4606 1800.62  4628.4 1798.03  4645.6 1792.19  4660.4 1781.71
  4675.6 1775.51  4724.7 1770.12  4746.9 1760.06    4763 1747.84    4775 1746.24
    4795 1746.83  4818.7 1739.73  4833.4 1732.38    4867 1734.99  4910.3 1735.23
  4938.9 1726.02  4958.4 1724.79  4973.9  1721.2  4996.9    1720  5006.3 1712.57
  5012.8 1712.36  5013.3 1711.86  5018.5 1712.36  5021.9 1715.03  5043.7 1722.91
  5090.5  1720.4  5168.5 1719.38  5224.7 1722.88  5296.5 1734.05  5364.1 1739.22
#Mann= 6 ,-1 , 0
  4572.9     .07       0  4645.6    .035       0    4775    .063       0
    4867    .035       0  5012.8    .035       0  5018.5    .035       0
Bank Sta=5012.8,5018.5
XS Rating Curve= 0 ,0
Exp/Cntr=0.3,0.1

Type RM Length L Ch R = 1 ,37080   ,630,630,630
BEGIN DESCRIPTION:
North Creek 74.0
END DESCRIPTION:
XS GIS Cut Line= 4
       1993781.2     13933573.98        1993575.       13933525.
      1993497.57     13933518.47      1993225.05     13933674.97
#Sta/Elev= 30
  4783.2  1763.8    4809  1739.9  4818.3 1733.27  4821.4 1732.22  4827.5 1730.91
  4883.9 1733.43  4895.4 1733.31  4916.9 1736.91  4929.3 1736.76  4941.6 1734.95
  4953.2 1731.83  4964.4 1726.86  4969.3 1722.83  4981.7 1717.38  5000.1 1706.34
  5005.3 1705.05  5012.1 1706.01  5018.3 1704.69  5018.8 1704.19    5024 1704.69
  5024.7 1706.81  5030.2  1712.6  5033.2 1713.25  5071.9 1711.22  5175.9 1712.55
  5234.9 1714.85  5307.5 1715.33  5324.8 1716.46    5349 1723.77  5387.1 1724.23
#Mann= 4 ,-1 , 0
  4783.2    .063       0  4883.9    .035       0  5018.3    .035       0
    5024    .035       0
#XS Ineff= 2 , 0
                         5035.66         1713.13
Permanent Ineff=
       F       F
Bank Sta=5018.3,5024
XS Rating Curve= 0 ,0
Exp/Cntr=0.3,0.1

Type RM Length L Ch R = 1 ,36450   ,297,297,297
BEGIN DESCRIPTION:
North Creek 73.0
END DESCRIPTION:
XS GIS Cut Line= 3
      1994162.21     13932936.82       1993577.8     13932954.89
      1993225.08     13933024.98
#Sta/Elev= 30
  4412.7 1740.59  4484.6 1731.54  4506.7 1727.88  4526.7 1728.89  4584.9 1721.67
  4617.9 1727.37    4675 1729.51  4689.4 1727.33  4699.7 1721.57    4708 1718.51
    4774 1715.46    4828 1704.77    4831 1708.43    4835 1709.37  4900.1 1704.14
  4951.1 1706.06  4954.1 1705.61  4963.1 1697.59  4976.5  1692.7    4977  1692.2
  4985.7  1692.7  4996.1  1697.7  4999.1 1703.66  5005.3 1705.59  5029.7 1703.82
  5103.4 1705.12  5283.6  1716.2  5320.3  1722.5  5344.8 1723.69    5357 1726.83
#Mann= 7 ,-1 , 0
  4412.7     .07       0  4484.6    .035       0  4526.7    .063       0
  4699.7    .035       0  4976.5    .035       0  4985.7    .035       0
  5103.4     .07       0
#XS Ineff= 2 , 0
         4833.57 1709.88
Permanent Ineff=
       F       F
Bank Sta=4976.5,4985.7
XS Rating Curve= 0 ,0
Exp/Cntr=0.3,0.1

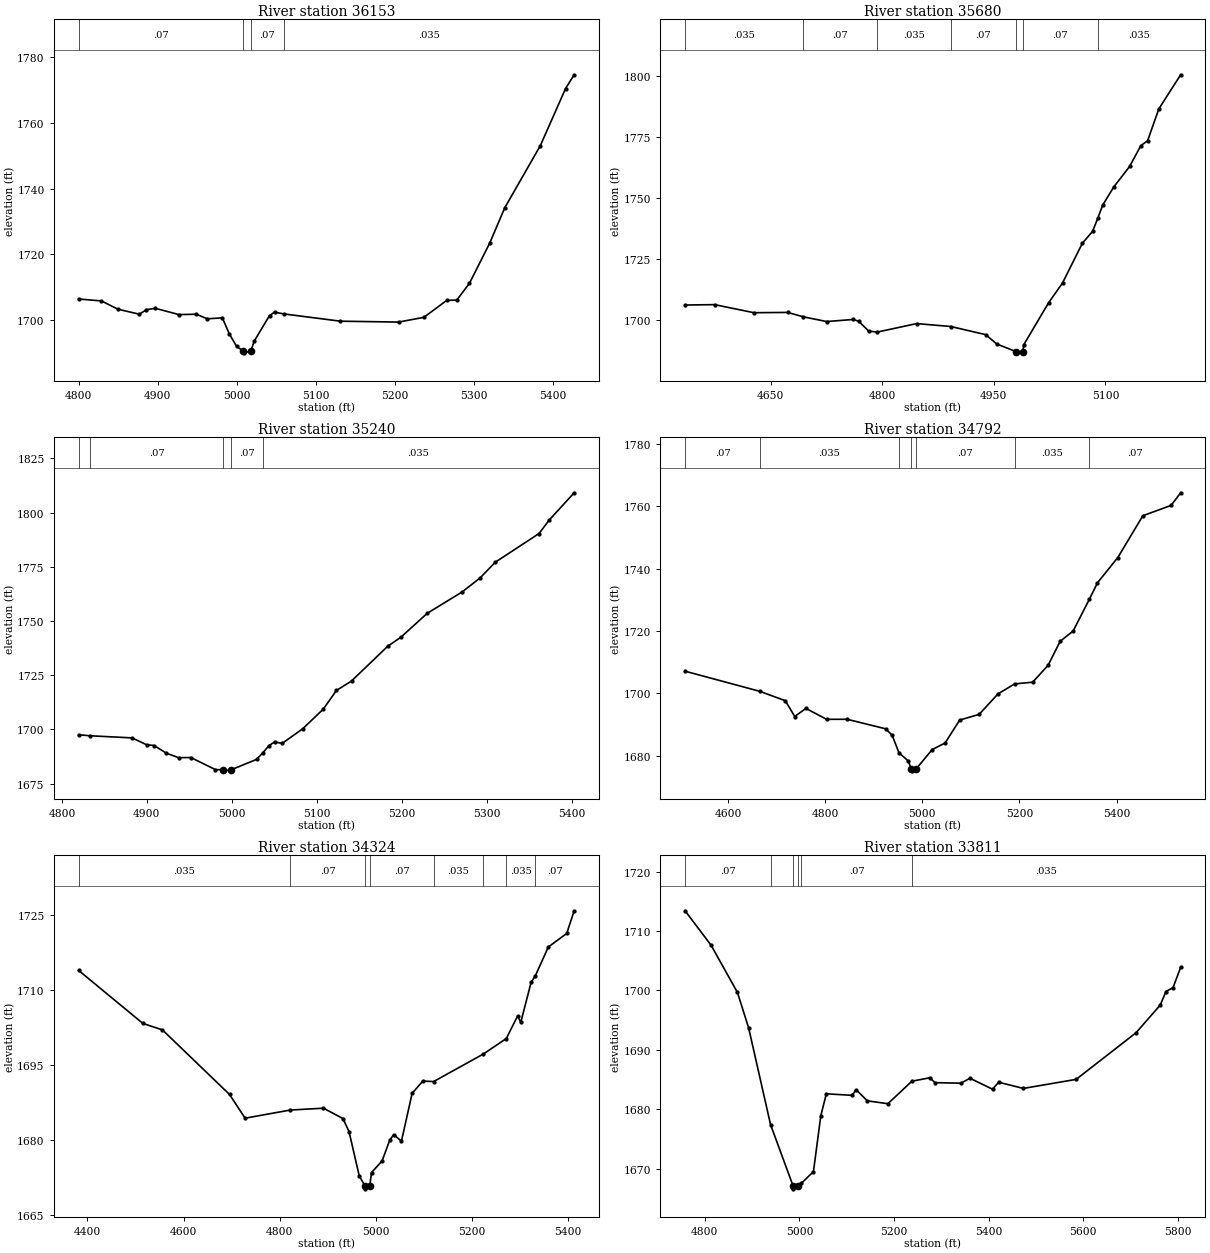
Type RM Length L Ch R = 1 ,36153   ,473,473,473
BEGIN DESCRIPTION:
North Creek 72.0
END DESCRIPTION:
XS GIS Cut Line= 3
      1993724.99       13932675.        1993525.       13932675.
        1993125.       13932525.
#Sta/Elev= 30
    4800 1706.48  4828.9 1705.89  4849.9 1703.36  4876.9 1701.86  4885.9 1703.24
    4897 1703.65    4927 1701.74  4948.9 1701.85    4963 1700.46  4981.9 1700.76
  4990.9 1695.79  4999.9 1692.11  5008.6 1690.63  5009.1 1690.13  5017.8 1690.63
  5022.5 1693.79  5041.6 1701.45  5048.1 1702.49  5059.5 1701.95  5131.3 1699.74
    5205 1699.47    5237 1700.91  5265.8 1706.04  5278.7 1706.17  5294.7 1711.26
  5320.3 1723.44  5339.4 1734.19  5384.4 1753.05  5416.3 1770.38  5427.2 1774.55
#Mann= 4 ,-1 , 0
    4800     .07       0  5008.6     .05       0  5017.8     .07       0
  5059.5    .035       0
#XS Ineff= 2 , 0
                         5053.85         1701.76
Permanent Ineff=
       F       F
Bank Sta=5008.6,5017.8
XS Rating Curve= 0 ,0
Exp/Cntr=0.3,0.1

Type RM Length L Ch R = 1 ,35680   ,440,440,440
BEGIN DESCRIPTION:
North Creek 71.0
END DESCRIPTION:
XS GIS Cut Line= 3
      1993835.77     13932307.62       1993376.5     13932249.97
      1993175.01       13932225.
#Sta/Elev= 30
  4535.2  1706.1  4574.9 1706.26  4627.6 1702.96    4673 1703.07  4694.3 1701.25
  4725.4 1699.34  4760.6 1700.18  4768.4 1699.49  4781.8 1695.46  4793.2 1695.01
  4846.3  1698.5  4892.2 1697.31    4939 1693.98  4954.1 1690.15  4979.8 1687.03
  4980.3 1686.53    4989 1687.03  4990.4  1689.9  5023.6 1706.99  5042.4 1715.14
    5069 1731.36  5082.8 1736.27  5090.1 1741.89  5096.2 1746.94  5111.3 1754.45
  5132.5  1762.8  5147.6 1771.33  5156.7 1773.34  5171.8 1786.38  5201.1 1800.34
#Mann= 7 ,-1 , 0
  4535.2    .035       0  4694.3     .07       0  4793.2    .035       0
  4892.2     .07       0  4979.8     .05       0    4989     .07       0
  5090.1    .035       0
Bank Sta=4979.8,4989
XS Rating Curve= 0 ,0
Exp/Cntr=0.3,0.1

Type RM Length L Ch R = 1 ,35240   ,448,448,448
BEGIN DESCRIPTION:
North Creek 70.0
END DESCRIPTION:
XS GIS Cut Line= 3
      1993725.04     13931975.03        1993575.       13931875.
      1993175.04       13931925.
#Sta/Elev= 30
  4819.7 1697.55    4833 1697.08  4882.5  1696.1  4899.8 1692.94  4908.6 1692.58
    4923 1689.04  4937.4 1686.96  4951.9 1687.04  4980.7 1681.46  4990.1  1681.4
  4990.6  1680.9  4999.4  1681.4  5029.2 1686.19  5036.5  1689.2  5043.8 1692.53
  5050.3 1694.21  5059.4 1693.58  5083.6 1700.33  5107.8  1709.4  5123.2 1717.97
    5141 1722.35  5183.4  1738.3  5199.3 1742.61  5230.1 1753.57    5271 1763.37
  5292.2 1769.83  5310.3 1777.16  5361.7 1790.36  5373.8 1796.62  5403.1 1809.17
#Mann= 5 ,-1 , 0
  4819.7    .035       0    4833     .07       0  4990.1     .05       0
  4999.4     .07       0  5036.5    .035       0
Bank Sta=4990.1,4999.4
XS Rating Curve= 0 ,0
Exp/Cntr=0.3,0.1

Type RM Length L Ch R = 1 ,34792   ,468,468,468
BEGIN DESCRIPTION:
North Creek 69.0
END DESCRIPTION:
XS GIS Cut Line= 3
      1994108.65     13931785.24        1993725.       13931475.
      1993251.13     13931243.69
#Sta/Elev= 30
  4511.4 1707.09  4665.4 1700.63  4717.9 1697.62  4737.2 1692.56  4760.3 1695.16
  4802.8 1691.66  4845.2 1691.67  4924.4 1688.62  4937.8 1686.57    4952  1680.9
  4971.4 1678.27  4977.3 1675.64  4977.8 1675.14  4986.7 1675.64  5020.3 1681.95
    5047 1684.08    5077 1691.42  5117.1 1693.25  5155.8  1699.8  5190.2 1703.02
  5227.3 1703.56    5259 1708.97    5284 1716.69  5310.6 1719.96  5344.1 1730.16
  5360.8 1735.43  5402.6 1743.52  5454.3 1756.94  5512.5 1760.26  5532.1  1764.3
#Mann= 7 ,-1 , 0
  4511.4     .07       0  4665.4    .035       0    4952     .07       0
  4977.3     .05       0  4986.7     .07       0  5190.2    .035       0
  5344.1     .07       0
Bank Sta=4977.3,4986.7
XS Rating Curve= 0 ,0
Exp/Cntr=0.3,0.1

Type RM Length L Ch R = 1 ,34324   ,513,513,513
BEGIN DESCRIPTION:
North Creek 68.0
END DESCRIPTION:
XS GIS Cut Line= 3
      1994389.22     13931490.08        1993925.       13931075.
      1993540.45     13930938.17
#Sta/Elev= 30
  4381.8 1713.88  4515.5 1703.27  4556.1 1701.98  4695.7 1689.06  4728.1 1684.31
  4822.2 1685.94  4891.2 1686.31  4931.6 1684.24  4944.3 1681.64  4965.5 1672.79
  4977.8 1670.67  4978.3 1670.17  4987.4 1670.67  4991.1 1673.44  5013.1 1675.75
    5029 1679.91  5037.3 1681.03  5053.3 1679.69  5075.6 1689.28  5097.8 1691.74
  5120.3 1691.64  5223.8 1697.15  5271.5 1700.25    5295 1704.77  5301.6 1703.49
  5323.1 1711.49  5331.9 1712.81    5359 1718.58  5397.2 1721.28  5412.7 1725.82
#Mann= 8 ,-1 , 0
  4381.8    .035       0  4822.2     .07       0  4977.8     .05       0
  4987.4     .07       0  5120.3    .035       0  5223.8     .07       0
  5271.5    .035       0  5331.9     .07       0
Bank Sta=4977.8,4987.4
XS Rating Curve= 0 ,0
Exp/Cntr=0.3,0.1

Type RM Length L Ch R = 1 ,33811   ,437,437,437
BEGIN DESCRIPTION:
North Creek 67.0
END DESCRIPTION:
XS GIS Cut Line= 4
      1994505.33     13931133.44      1994365.76     13930942.03
      1994068.97       13930632.      1993689.16      13930593.8
#Sta/Elev= 30
  4758.3  1713.4  4813.4 1707.59    4869 1699.67  4892.7  1693.7    4939 1677.45
  4986.6 1667.16  4987.1 1666.66  4996.3 1667.16  5004.2 1667.59  5029.7 1669.56
  5045.2 1678.92  5056.9 1682.63  5111.6 1682.38  5119.9 1683.32  5143.7 1681.45
  5187.1 1680.97  5237.8 1684.75  5275.8 1685.33  5286.8 1684.51  5341.6 1684.42
  5360.6 1685.25  5408.3 1683.41  5421.3 1684.58  5473.5 1683.54  5585.1 1685.06
  5711.7 1692.89    5763 1697.55    5775 1699.82  5790.1 1700.49  5806.1 1703.89
#Mann= 6 ,-1 , 0
  4758.3     .07       0    4939      .1       0  4986.6     .05       0
  4996.3      .1       0  5004.2     .07       0  5237.8    .035       0
Bank Sta=4986.6,4996.3
XS Rating Curve= 0 ,0
Exp/Cntr=0.3,0.1

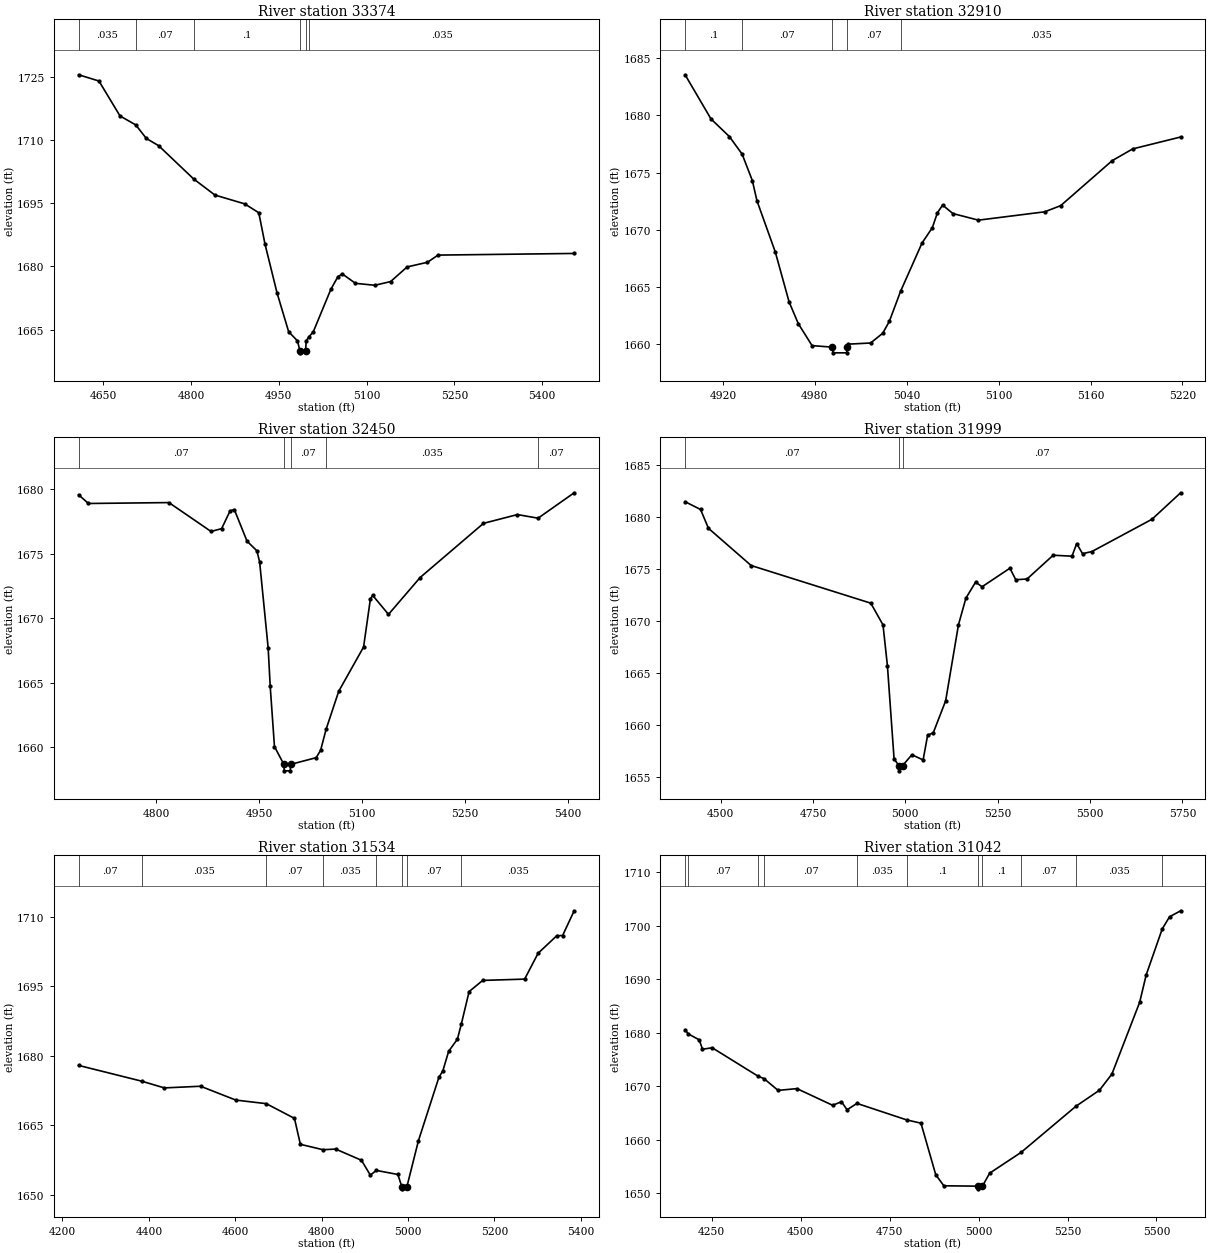
Type RM Length L Ch R = 1 ,33374   ,464,464,464
BEGIN DESCRIPTION:
North Creek 66.0
END DESCRIPTION:
XS GIS Cut Line= 3
      1994816.72      13930533.2        1994425.       13930525.
       1993970.7      13930511.9
#Sta/Elev= 30
  4608.2 1725.44  4642.9 1723.96  4678.9 1715.67  4705.8 1713.54  4723.9 1710.33
  4744.9 1708.61  4804.4 1700.75  4840.9 1696.91  4891.9 1694.81  4915.9  1692.7
  4926.5 1685.26  4947.1 1673.66  4966.9 1664.47  4981.9 1662.32  4986.1 1659.97
  4986.6 1659.47  4995.8 1659.97  4996.9  1662.3  5001.5 1663.27  5008.8 1664.42
  5038.9 1674.52    5051 1677.54  5058.6 1678.18    5081 1675.96    5114  1675.5
    5141 1676.38  5169.2 1679.85    5204 1680.96    5222 1682.66  5454.5 1683.05
#Mann= 6 ,-1 , 0
  4608.2    .035       0  4705.8     .07       0  4804.4      .1       0
  4986.1     .05       0  4995.8      .1       0  5001.5    .035       0
Bank Sta=4986.1,4995.8
XS Rating Curve= 0 ,0
Exp/Cntr=0.3,0.1

Type RM Length L Ch R = 1 ,32910   ,460,460,460
BEGIN DESCRIPTION:
North Creek 65.0
END DESCRIPTION:
XS GIS Cut Line= 3
      1994474.96       13930075.        1994375.       13930075.
      1994175.06     13930174.97
#Sta/Elev= 30
  4895.3 1683.56  4912.2  1679.7  4924.2 1678.16  4932.5 1676.63  4939.2 1674.31
  4942.2 1672.55  4954.2 1668.06  4963.2  1663.7  4969.2  1661.8  4978.2 1659.88
  4991.4 1659.75  4991.9 1659.25  5000.7 1659.25  5001.2 1659.75  5001.8 1660.01
  5016.4 1660.11  5024.3 1660.96  5028.6 1661.99    5036 1664.64    5050 1668.86
  5056.7 1670.19    5060 1671.49  5063.4 1672.17  5070.1 1671.43  5086.8 1670.85
  5130.1 1671.58  5140.5 1672.12  5174.1 1676.05  5187.5 1677.08  5218.8 1678.12
#Mann= 5 ,-1 , 0
  4895.3      .1       0  4932.5     .07       0  4991.4     .05       0
  5001.2     .07       0    5036    .035       0
Bank Sta=4991.4,5001.2
XS Rating Curve= 0 ,0
Exp/Cntr=0.3,0.1

Type RM Length L Ch R = 1 ,32450   ,451,451,451
BEGIN DESCRIPTION:
North Creek 64.0
END DESCRIPTION:
XS GIS Cut Line= 3
      1994580.04     13929604.46        1994275.       13929675.
      1993902.77     13929844.02
#Sta/Elev= 30
  4686.9 1679.57  4701.2  1678.9  4818.4 1678.97  4879.8 1676.73  4895.2 1676.95
  4907.5 1678.32  4913.7 1678.43  4932.2 1675.98  4946.6 1675.23  4950.6 1674.36
    4963  1667.7    4966 1664.71  4972.2 1660.05  4985.9 1658.67  4986.4 1658.17
  4995.2 1658.17  4995.7 1658.67  5032.9 1659.19  5039.4 1659.76  5047.4 1661.39
  5065.8 1664.34    5102 1667.77  5111.9 1671.48  5115.2 1671.78  5138.3  1670.3
  5184.4 1673.16  5276.7 1677.36  5326.1 1678.04  5356.2 1677.76  5408.8 1679.73
#Mann= 5 ,-1 , 0
  4686.9     .07       0  4985.9     .05       0  4995.7     .07       0
  5047.4    .035       0  5356.2     .07       0
Bank Sta=4985.9,4995.7
XS Rating Curve= 0 ,0
Exp/Cntr=0.3,0.1

Type RM Length L Ch R = 1 ,31999   ,465,465,465
BEGIN DESCRIPTION:
North Creek 63.0
END DESCRIPTION:
XS GIS Cut Line= 5
      1994801.21     13929399.14      1994477.61     13929271.07
        1994225.       13929275.      1994042.23     13929307.17
      1993855.99     13929829.95
#Sta/Elev= 30
  4403.9  1681.5  4445.8 1680.75    4467 1678.94  4582.6 1675.35  4906.5 1671.72
  4939.5 1669.63  4951.5 1665.69  4969.5 1656.72  4982.5 1656.06    4983 1655.56
  4992.4 1656.06  5017.7 1657.11  5048.1 1656.61  5060.3 1658.99  5075.6 1659.23
  5109.1 1662.31  5143.8 1669.64  5163.9  1672.2  5190.1 1673.75  5207.6  1673.3
    5283 1675.09  5298.9 1673.98  5329.4 1674.05  5400.1 1676.34    5451 1676.25
  5463.8 1677.46  5479.6 1676.49  5505.2  1676.7  5667.6 1679.81  5745.1 1682.36
#Mann= 3 ,-1 , 0
  4403.9     .07       0  4982.5     .05       0  4992.4     .07       0
Bank Sta=4982.5,4992.4
XS Rating Curve= 0 ,0
Exp/Cntr=0.3,0.1

Type RM Length L Ch R = 1 ,31534   ,492,492,492
BEGIN DESCRIPTION:
North Creek 62.0
END DESCRIPTION:
XS GIS Cut Line= 4
      1994759.57     13929291.34      1994466.39     13928951.85
        1994175.       13928825.      1993830.55     13928662.78
#Sta/Elev= 30
  4237.4 1677.92  4384.4 1674.49  4435.8 1673.06  4519.7 1673.42  4601.3 1670.43
  4671.7 1669.66    4737 1666.48  4750.7 1660.88  4802.9 1659.71  4832.4 1659.85
  4892.1 1657.43  4912.6 1654.23  4926.5 1655.24  4976.4 1654.36  4985.4 1651.76
  4985.9 1651.26  4997.4 1651.76    5024 1661.66  5071.4 1675.35  5080.4 1676.71
  5093.9 1680.96  5114.2 1683.59  5123.4  1686.9  5141.3 1693.87  5172.8 1696.28
  5269.8 1696.56    5301 1702.14  5344.3 1705.94  5357.7 1705.97  5384.5 1711.32
#Mann= 8 ,-1 , 0
  4237.4     .07       0  4384.4    .035       0  4671.7     .07       0
  4802.9    .035       0  4926.5     .07       0  4985.4     .05       0
  4997.4     .07       0  5123.4    .035       0
Bank Sta=4985.4,4997.4
XS Rating Curve= 0 ,0
Exp/Cntr=0.3,0.1

Type RM Length L Ch R = 1 ,31042   ,423,423,423
BEGIN DESCRIPTION:
North Creek 61.0
END DESCRIPTION:
XS GIS Cut Line= 4
      1994963.99     13929144.92      1994723.66     13928627.94
        1994525.       13928475.      1993952.86     13928468.28
#Sta/Elev= 30
    4175 1680.52    4184 1679.76  4214.7 1678.66  4223.9  1676.9  4251.1 1677.18
  4381.3 1671.82  4396.8 1671.42  4436.4 1669.22  4489.3 1669.55  4589.7 1666.44
  4614.6  1667.1  4630.4  1665.6  4658.1 1666.79  4798.3  1663.7    4838  1663.1
  4879.6 1653.47  4902.3 1651.41  4998.7 1651.34  4999.2 1650.84  5010.8 1651.34
  5031.1 1653.76  5119.8 1657.66  5273.7 1666.26  5339.8 1669.25  5374.8 1672.27
  5452.8 1685.66  5471.3 1690.81  5516.2 1699.35  5536.8 1701.63    5568 1702.75
#Mann= 11 ,-1 , 0
    4175    .035       0    4184     .07       0  4381.3    .035       0
  4396.8     .07       0  4658.1    .035       0  4798.3      .1       0
  4998.7     .05       0  5010.8      .1       0  5119.8     .07       0
  5273.7    .035       0  5516.2     .07       0
Bank Sta=4998.7,5010.8
XS Rating Curve= 0 ,0
Exp/Cntr=0.3,0.1