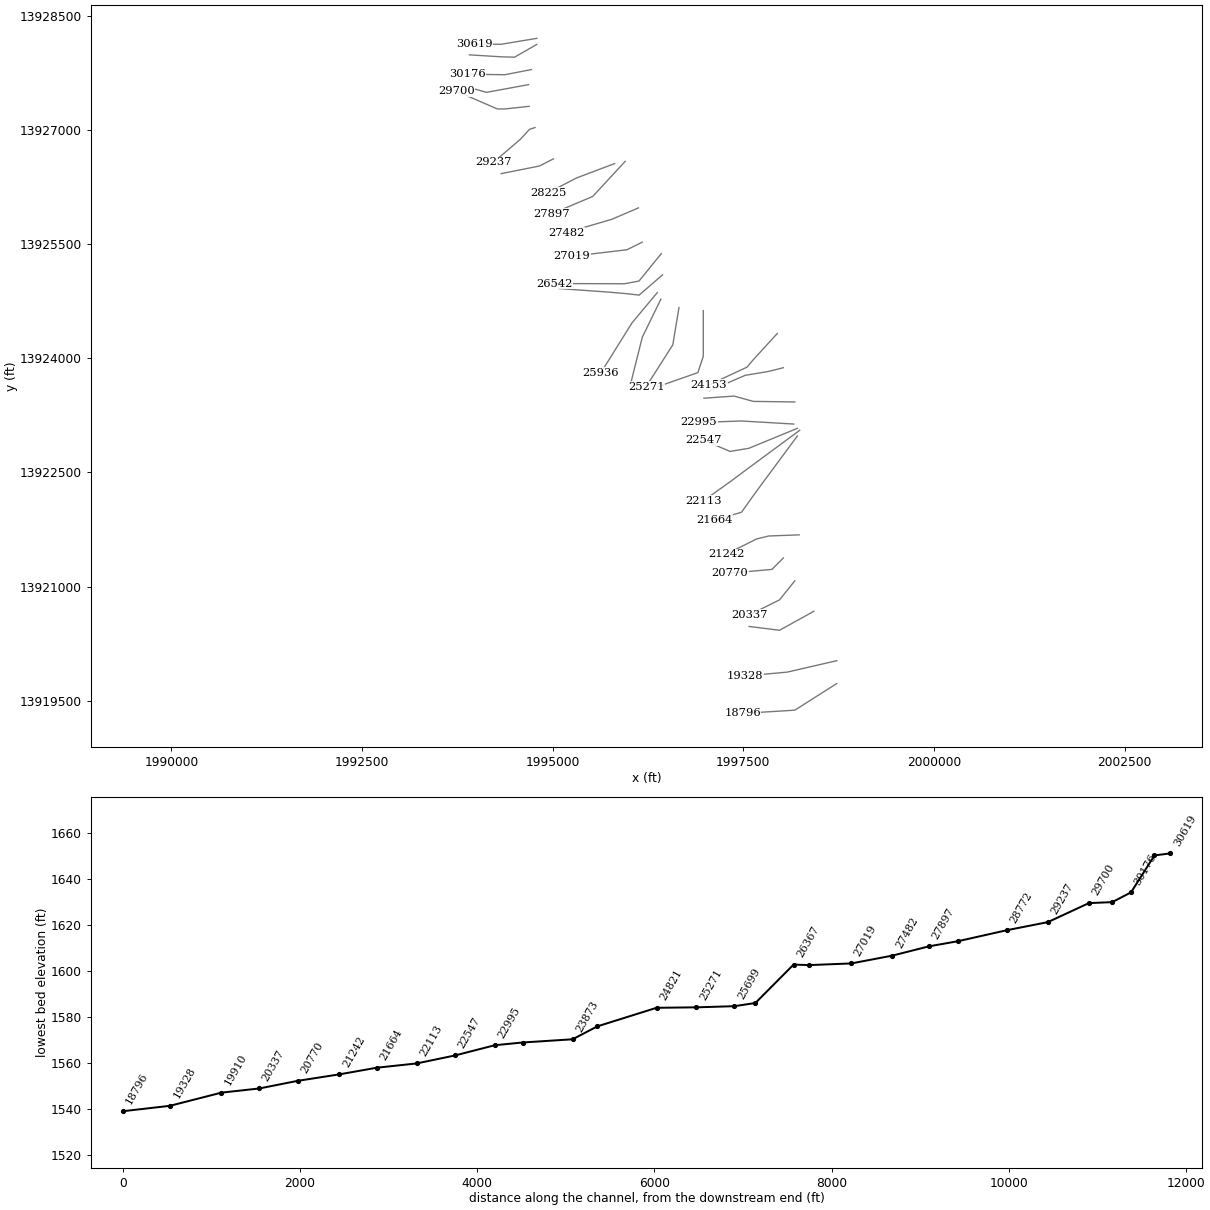
HEC-RAS study North Creek.prj: North Creek Base Level Engineering

--- North Creek.g01 (geometry) --- (continued)

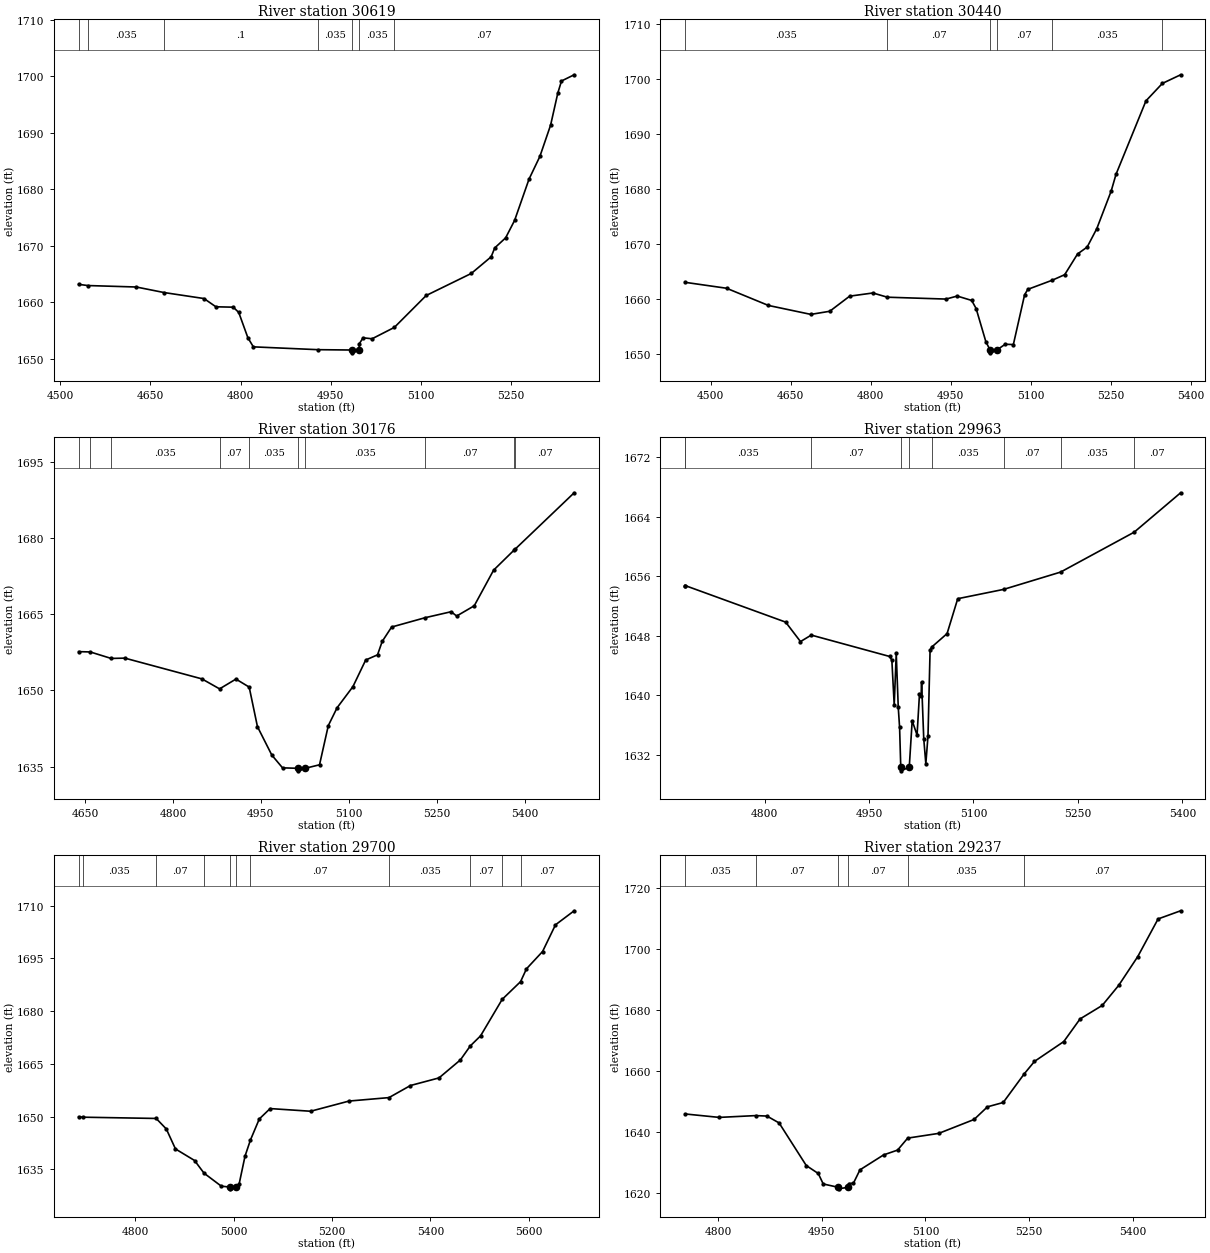
Type RM Length L Ch R = 1 ,30619   ,179,179,179
BEGIN DESCRIPTION:
North Creek 60.0
END DESCRIPTION:
XS GIS Cut Line= 3
      1994792.74     13928202.96        1994325.       13928125.
      1993974.99       13928125.
#Sta/Elev= 30
  4530.6 1663.18  4545.8 1662.97  4626.6 1662.71  4672.7 1661.73  4739.1 1660.67
  4758.9 1659.21  4787.8 1659.14  4796.9 1658.21  4812.1 1653.73  4821.2 1652.12
  4928.6 1651.62  4984.8 1651.56  4985.3 1651.06    4997 1651.56  4997.6  1652.7
  5003.7 1653.72  5018.7 1653.55  5055.7 1655.56  5108.7 1661.21  5183.7 1665.11
  5216.7 1668.05  5222.7 1669.63  5240.8 1671.41  5255.7 1674.49  5279.7  1681.8
  5297.8 1685.83  5315.6 1691.36  5327.6 1697.04  5333.7 1699.17  5354.8 1700.27
#Mann= 7 ,-1 , 0
  4530.6     .07       0  4545.8    .035       0  4672.7      .1       0
  4928.6    .035       0  4984.8    .035       0    4997    .035       0
  5055.7     .07       0
Bank Sta=4984.8,4997
XS Rating Curve= 0 ,0
Exp/Cntr=0.3,0.1

Type RM Length L Ch R = 1 ,30440   ,264,264,264
BEGIN DESCRIPTION:
North Creek 59.1
END DESCRIPTION:
XS GIS Cut Line= 4
      1994791.47     13928122.66      1994500.64     13927955.54
       1994329.2     13927959.88      1993908.22     13927985.92
#Sta/Elev= 30
  4452.3 1663.04    4530 1661.96  4608.4 1658.83    4688  1657.2  4723.4 1657.77
  4760.7 1660.52  4804.3  1661.1  4831.3 1660.33  4941.3 1659.99  4962.3 1660.54
  4989.4 1659.74  4997.7 1658.27    5016 1652.22    5024  1650.7  5024.5  1650.2
  5036.2  1650.7  5052.2 1651.76  5067.5 1651.71  5088.6 1660.78  5094.6 1661.76
  5140.3 1663.42  5163.7 1664.43  5187.8  1668.2  5205.8 1669.46  5223.8  1672.8
  5250.8 1679.65  5259.9 1682.71    5316 1696.08  5346.8 1699.26    5381 1700.83
#Mann= 6 ,-1 , 0
  4452.3    .035       0  4831.3     .07       0    5024     .05       0
  5036.2     .07       0  5140.3    .035       0  5346.8     .07       0
Bank Sta=5024,5036.2
XS Rating Curve= 0 ,0
Exp/Cntr=0.3,0.1

Type RM Length L Ch R = 1 ,30176   ,213,213,213
BEGIN DESCRIPTION:
North Creek 59.0
END DESCRIPTION:
XS GIS Cut Line= 3
      1994721.47     13927792.97        1994375.       13927725.
      1993882.61     13927731.05
#Sta/Elev= 30
  4639.1 1657.65  4658.9 1657.59  4694.6 1656.31    4718 1656.37  4849.4 1652.28
  4879.6 1650.31  4907.5 1652.24  4930.1 1650.66  4944.2 1642.86  4968.7 1637.26
    4987 1634.74  5013.4 1634.65  5013.9 1634.15  5025.6 1634.65  5050.1 1635.34
  5065.1 1643.07  5080.1 1646.59  5107.1 1650.75  5128.9    1656  5149.1 1657.02
    5157 1659.65  5173.1  1662.5  5230.3 1664.34  5274.7 1665.52  5284.1 1664.67
  5314.1 1666.69  5347.1 1673.71  5381.8 1677.64  5384.1 1677.88  5484.6 1688.97
#Mann= 10 ,-1 , 0
  4639.1    .035       0  4658.9     .07       0  4694.6    .035       0
  4879.6     .07       0  4930.1    .035       0  5013.4    .035       0
  5025.6    .035       0  5230.3     .07       0  5381.8    .035       0
  5384.1     .07       0
Bank Sta=5013.4,5025.6
XS Rating Curve= 0 ,0
Exp/Cntr=0.3,0.1

Type RM Length L Ch R = 1 ,29963   ,263,263,263
BEGIN DESCRIPTION:
Mapping XS 7b4ae1ff
END DESCRIPTION:
XS GIS Cut Line= 3
      1994684.07     13927594.65      1994133.16     13927493.24
      1993987.36     13927534.16
#Sta/Elev= 30
  4685.9 1654.75  4686.1 1654.74  4830.3 1649.84  4851.6 1647.23  4867.1  1648.1
  4979.7 1645.23  4982.8 1644.74  4986.2 1638.71  4989.1 1645.64    4992  1638.4
  4993.9 1635.75  4995.6 1630.39  4996.1 1629.89  5007.8 1630.39    5012 1636.62
    5019 1634.68  5022.5 1640.25  5024.8 1639.91  5025.5 1641.82  5028.6 1634.19
  5031.6 1630.85  5034.7 1634.55  5037.7  1646.1    5040 1646.49  5062.1  1648.3
  5077.4 1652.98  5143.3 1654.23  5225.1 1656.55  5330.7  1661.9  5397.5 1667.19
#Mann= 9 ,-1 , 0
  4685.9     .07       0  4686.1    .035       0  4867.1     .07       0
  4995.6     .05       0  5007.8     .07       0    5040    .035       0
  5143.3     .07       0  5225.1    .035       0  5330.7     .07       0
Bank Sta=4995.6,5007.8
XS Rating Curve= 0 ,0
Exp/Cntr=0.3,0.1

Type RM Length L Ch R = 1 ,29700   ,463,463,463
BEGIN DESCRIPTION:
North Creek 58.0
END DESCRIPTION:
XS GIS Cut Line= 4
      1994692.15     13927309.84        1994375.       13927275.
        1994275.       13927275.       1993736.2     13927509.31
#Sta/Elev= 30
  4685.3 1649.97  4693.4 1649.85  4842.8 1649.49  4863.4  1646.5    4882 1640.82
  4920.8 1637.53    4940 1633.93  4975.1 1630.23  4992.8 1629.97  4993.3 1629.47
    5005 1629.97  5011.3 1630.83  5023.3 1638.77  5034.3 1643.36  5052.3 1649.35
  5074.3  1652.3  5156.6 1651.54  5234.6 1654.44  5315.7 1655.42  5359.4 1658.86
  5417.3 1661.02  5460.8 1666.14  5480.9 1670.12  5501.8 1672.99  5545.7 1683.37
    5583  1688.4    5595 1692.05  5627.7 1696.97  5653.9 1704.56  5691.9 1708.56
#Mann= 11 ,-1 , 0
  4685.3     .07       0  4693.4    .035       0  4842.8     .07       0
    4940    .035       0  4992.8    .035       0    5005    .035       0
  5034.3     .07       0  5315.7    .035       0  5480.9     .07       0
  5545.7    .035       0    5583     .07       0
Bank Sta=4992.8,5005
XS Rating Curve= 0 ,0
Exp/Cntr=0.3,0.1

Type RM Length L Ch R = 1 ,29237   ,465,465,465
BEGIN DESCRIPTION:
North Creek 57.0
END DESCRIPTION:
XS GIS Cut Line= 4
      1994768.77     13927031.18      1994696.57     13927006.62
        1994575.       13926875.      1994225.01     13926575.01
#Sta/Elev= 30
  4752.6 1645.79  4801.9 1644.66  4854.6 1645.25  4870.9  1645.1  4888.5 1642.84
  4927.8 1628.85  4945.1 1626.25  4952.3 1622.81  4974.1 1621.71  4974.6 1621.21
  4987.7 1621.71  4989.1  1622.9    4996 1623.08  5005.4 1627.44  5039.5 1632.34
  5059.8 1633.93  5074.4 1637.86  5119.4 1639.42  5170.4 1643.98  5189.7 1648.13
  5212.5 1649.55  5242.8 1658.93  5257.7 1663.04  5300.1 1669.56  5323.6 1676.98
  5355.6  1681.4  5379.4 1687.98    5407 1697.44  5436.4  1709.8    5469 1712.48
#Mann= 6 ,-1 , 0
  4752.6    .035       0  4854.6     .07       0  4974.1     .05       0
  4987.7     .07       0  5074.4    .035       0  5242.8     .07       0
Bank Sta=4974.1,4987.7
XS Rating Curve= 0 ,0
Exp/Cntr=0.3,0.1

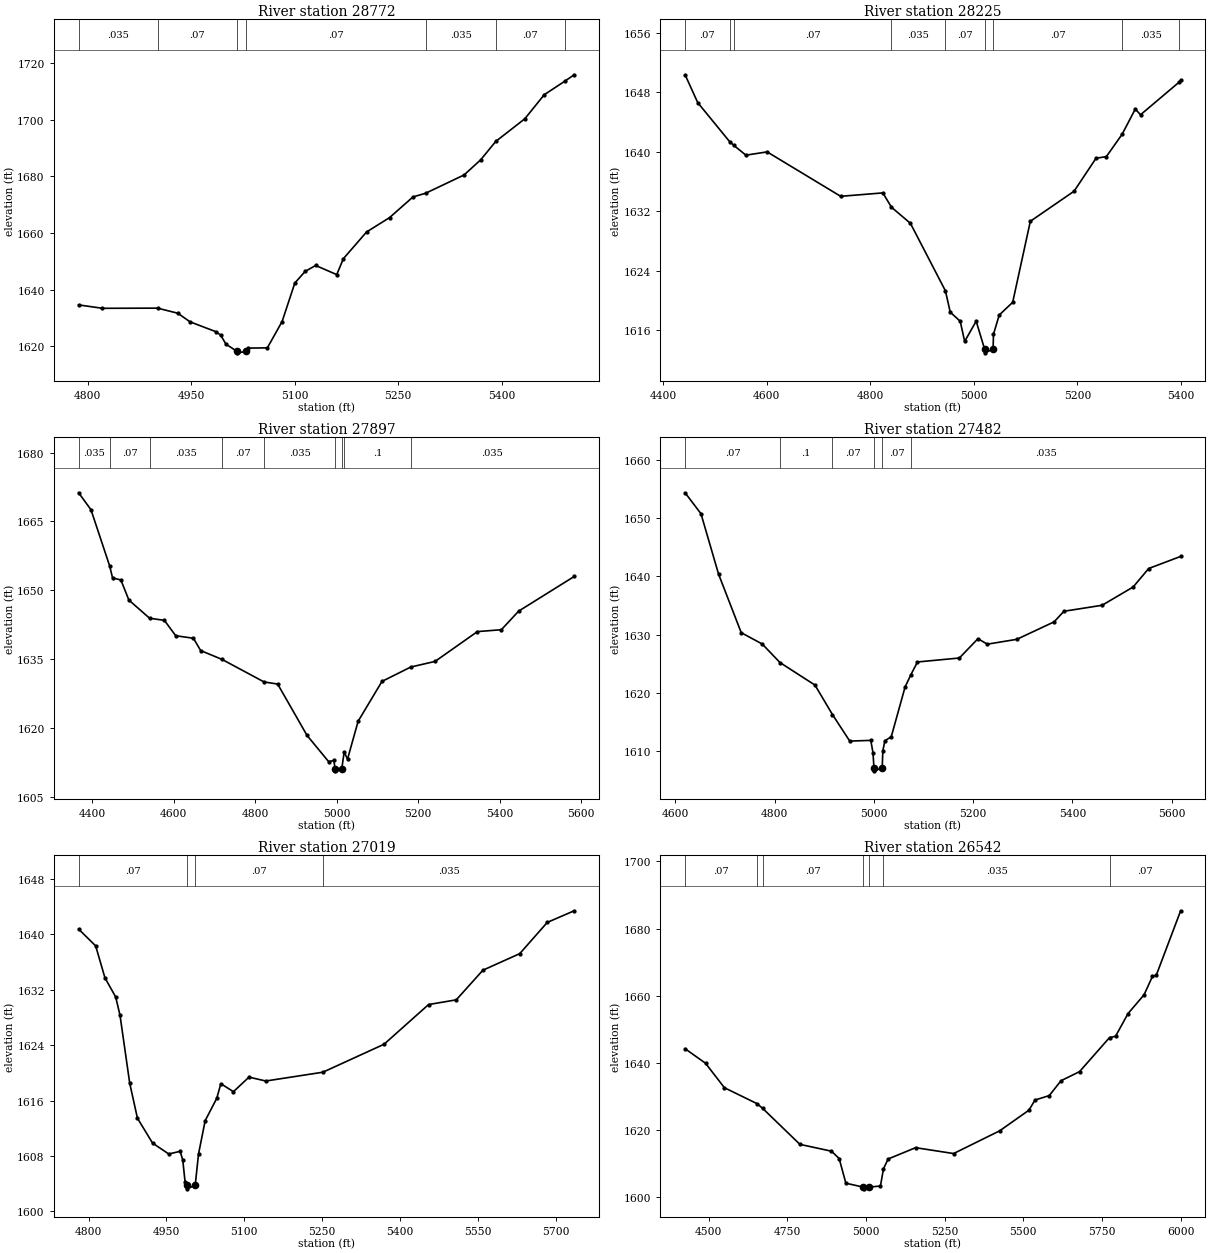
Type RM Length L Ch R = 1 ,28772   ,547,547,547
BEGIN DESCRIPTION:
North Creek 56.0
END DESCRIPTION:
XS GIS Cut Line= 3
      1995010.73     13926619.64        1994825.       13926525.
      1994324.96     13926424.99
#Sta/Elev= 30
  4786.8  1634.6  4821.4  1633.4  4901.2 1633.46  4930.6 1631.66  4948.4 1628.61
  4986.2 1625.11  4992.9 1623.87  5000.3 1620.77  5016.5 1618.18    5017 1617.68
  5030.1 1618.18  5032.9 1619.35  5060.4 1619.44  5081.8 1628.74  5100.2 1642.31
  5115.1 1646.41  5130.4 1648.52    5161 1645.29  5170.6 1650.91  5204.2 1660.34
  5237.5  1665.4  5271.5 1672.71  5289.7    1674  5345.6 1680.47  5369.4 1685.75
  5391.6 1692.32  5433.7 1700.31  5461.8 1708.79  5491.6 1713.56  5505.2 1715.83
#Mann= 7 ,-1 , 0
  4786.8    .035       0  4901.2     .07       0  5016.5     .05       0
  5030.1     .07       0  5289.7    .035       0  5391.6     .07       0
  5491.6    .035       0
Bank Sta=5016.5,5030.1
XS Rating Curve= 0 ,0
Exp/Cntr=0.3,0.1

Type RM Length L Ch R = 1 ,28225   ,328,328,328
BEGIN DESCRIPTION:
Mapping XS 46b8816b
END DESCRIPTION:
XS GIS Cut Line= 3
       1995812.9     13926557.34      1995313.78     13926368.54
      1994938.38     13926173.25
#Sta/Elev= 30
  4442.4 1650.37  4466.8 1646.62  4528.4 1641.37  4536.4 1640.87  4559.8 1639.55
  4600.8 1639.99  4742.8 1634.01  4824.2 1634.47  4840.9 1632.54  4877.4 1630.38
  4945.1 1621.28  4954.3 1618.42  4973.6 1617.19  4982.2 1614.48  5004.4  1617.2
  5020.7 1613.44  5021.2 1612.94  5037.1 1613.44  5037.8 1615.43  5048.9 1618.03
  5074.9 1619.74    5109 1630.65  5193.5  1634.7  5235.8 1639.13  5255.8 1639.36
  5286.1 1642.35  5311.6 1645.75  5321.8 1644.99    5397 1649.42  5399.2 1649.63
#Mann= 9 ,-1 , 0
  4442.4     .07       0  4528.4    .035       0  4536.4     .07       0
  4840.9    .035       0  4945.1     .07       0  5020.7     .05       0
  5037.1     .07       0  5286.1    .035       0    5397     .07       0
Bank Sta=5020.7,5037.1
XS Rating Curve= 0 ,0
Exp/Cntr=0.3,0.1

Type RM Length L Ch R = 1 ,27897   ,415,415,415
BEGIN DESCRIPTION:
North Creek 54.0
END DESCRIPTION:
XS GIS Cut Line= 3
      1995951.22     13926587.18        1995525.       13926125.
      1994983.51     13925896.07
#Sta/Elev= 30
  4366.7 1671.25    4397 1667.56    4443 1655.28    4450 1652.71  4470.4 1652.27
  4490.1 1647.88  4540.9 1643.93  4577.2 1643.47  4605.1 1640.12  4648.6 1639.57
  4666.3 1636.89  4718.6 1634.97  4822.1 1630.05  4855.3  1629.6  4927.4 1618.42
  4980.5  1612.7  4993.3 1612.96  4996.3  1611.2  4996.8  1610.7  5012.8  1611.2
  5018.7 1614.82  5026.8 1613.23  5052.9  1621.5  5111.5 1630.18  5182.1  1633.3
  5241.8 1634.53  5345.7 1641.02  5404.6 1641.43    5447 1645.48  5583.3 1653.02
#Mann= 9 ,-1 , 0
  4366.7    .035       0    4443     .07       0  4540.9    .035       0
  4718.6     .07       0  4822.1    .035       0  4996.3    .035       0
  5012.8    .035       0  5018.7      .1       0  5182.1    .035       0
Bank Sta=4996.3,5012.8
XS Rating Curve= 0 ,0
Exp/Cntr=0.3,0.1

Type RM Length L Ch R = 1 ,27482   ,463,463,463
BEGIN DESCRIPTION:
North Creek 53.0
END DESCRIPTION:
XS GIS Cut Line= 3
      1996125.03     13925975.01        1995775.       13925825.
       1995182.3     13925650.78
#Sta/Elev= 30
  4619.4 1654.32  4651.4 1650.73  4686.8 1640.39  4732.5 1630.34  4774.8  1628.4
  4810.6 1625.22  4881.1 1621.36  4916.4  1616.3  4951.2 1611.76  4993.6 1611.88
    4998 1609.77    5000 1607.16  5000.5 1606.66  5016.6 1607.16  5017.9 1610.11
    5022  1611.8  5034.9 1612.52  5062.7 1621.03  5074.6 1623.17  5087.7 1625.32
  5172.1    1626  5209.6 1629.31  5228.4 1628.37  5287.8  1629.2  5362.9 1632.19
  5382.8 1634.01  5459.8 1635.04  5522.3 1638.17  5553.6 1641.34    5618 1643.41
#Mann= 6 ,-1 , 0
  4619.4     .07       0  4810.6      .1       0  4916.4     .07       0
    5000     .05       0  5016.6     .07       0  5074.6    .035       0
Bank Sta=5000,5016.6
XS Rating Curve= 0 ,0
Exp/Cntr=0.3,0.1

Type RM Length L Ch R = 1 ,27019   ,477,477,477
BEGIN DESCRIPTION:
North Creek 52.0
END DESCRIPTION:
XS GIS Cut Line= 3
      1996174.97     13925524.98        1995975.       13925425.
      1995249.65       13925339.
#Sta/Elev= 30
    4781 1640.76  4813.8 1638.34  4831.6 1633.74  4852.4 1630.95  4860.7  1628.3
  4879.3 1618.53  4894.2 1613.46  4923.3 1609.87  4954.6 1608.29  4976.5 1608.68
  4981.5  1607.4  4985.9 1604.27  4988.8 1603.76  4989.3 1603.26  5005.4 1603.76
  5011.8 1608.28  5024.6  1613.1  5046.9 1616.33  5054.8 1618.44    5079 1617.29
    5109 1619.39  5141.4 1618.83  5251.2  1620.1    5369 1624.14  5454.7 1629.87
    5508 1630.55  5559.3 1634.83  5630.2 1637.22  5683.2 1641.73    5735 1643.41
#Mann= 4 ,-1 , 0
    4781     .07       0  4988.8     .05       0  5005.4     .07       0
  5251.2    .035       0
Bank Sta=4988.8,5005.4
XS Rating Curve= 0 ,0
Exp/Cntr=0.3,0.1

Type RM Length L Ch R = 1 ,26542   ,175,175,175
BEGIN DESCRIPTION:
North Creek 51.0
END DESCRIPTION:
XS GIS Cut Line= 4
      1996424.98     13925374.97      1996131.99     13925013.69
      1995941.43     13924978.12      1995025.94     13924980.77
#Sta/Elev= 30
  4425.6 1644.23  4490.5 1639.92  4550.5 1632.63  4653.8 1627.91  4671.9  1626.5
  4790.3 1615.78  4890.7 1613.74  4915.1 1611.56  4936.4 1604.22  4992.2 1603.04
  4992.7 1602.54  5008.9 1603.04  5046.3 1603.38  5055.9 1608.51  5070.7 1611.42
    5158 1614.79  5278.7 1613.04    5425  1619.8    5518 1625.94  5537.5 1628.97
  5582.6 1630.29    5620 1634.71  5678.9 1637.42  5774.2 1647.56  5793.2 1647.93
    5833 1654.71    5884  1660.3  5910.5 1665.76  5922.6 1666.09  6000.1 1685.29
#Mann= 7 ,-1 , 0
  4425.6     .07       0  4653.8    .035       0  4671.9     .07       0
  4992.2     .05       0  5008.9     .07       0  5055.9    .035       0
  5774.2     .07       0
Bank Sta=4992.2,5008.9
XS Rating Curve= 0 ,0
Exp/Cntr=0.3,0.1

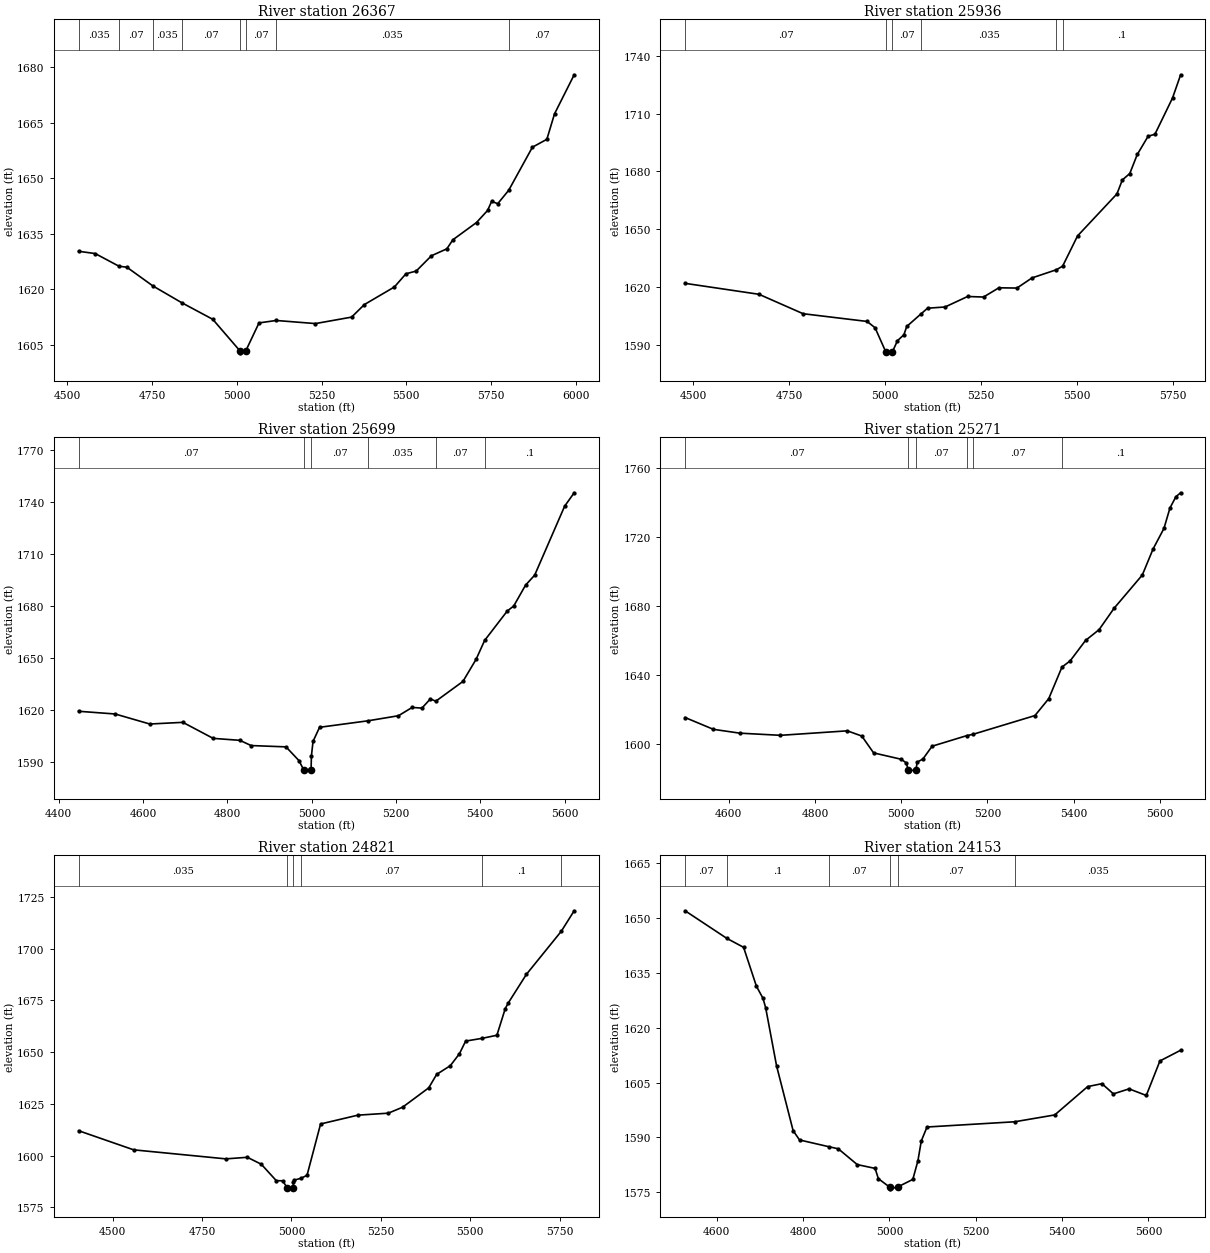
Type RM Length L Ch R = 1 ,26367   ,431,431,431
BEGIN DESCRIPTION:
North Creek 51.1
END DESCRIPTION:
XS GIS Cut Line= 5
      1996440.73     13925095.29      1996132.58     13924828.37
      1995991.52     13924845.73      1995744.13     13924867.43
       1995082.2     13924915.18
#Sta/Elev= 30
  4533.5 1630.25  4582.4 1629.63  4652.4 1626.21  4675.9 1625.93  4752.5 1620.87
  4837.2 1616.35  4929.1 1611.84  5009.7 1603.26  5010.2 1602.76  5026.4 1603.26
  5065.6 1610.86  5116.3 1611.52  5232.1 1610.68  5338.7 1612.43  5376.5 1615.83
    5465 1620.59  5499.1 1624.16  5529.2 1624.89  5574.3 1629.04  5619.7 1630.91
  5637.5 1633.36  5707.2 1638.03  5739.8 1641.29  5751.8 1643.76  5769.8 1643.13
  5802.2 1646.76  5872.1 1658.42  5914.7 1660.55  5937.3 1667.44  5995.3 1678.02
#Mann= 8 ,-1 , 0
  4533.5    .035       0  4652.4     .07       0  4752.5    .035       0
  4837.2     .07       0  5009.7     .05       0  5026.4     .07       0
  5116.3    .035       0  5802.2     .07       0
Bank Sta=5009.7,5026.4
XS Rating Curve= 0 ,0
Exp/Cntr=0.3,0.1

Type RM Length L Ch R = 1 ,25936   ,237,237,237
BEGIN DESCRIPTION:
North Creek 50.0
END DESCRIPTION:
XS GIS Cut Line= 3
      1996371.96      13924862.2      1996041.63     13924465.79
      1995631.36     13923808.06
#Sta/Elev= 30
  4478.9 1622.06  4671.4 1616.39  4786.4 1606.33  4953.1 1602.33  4973.9 1599.06
  5001.8 1586.57  5002.3 1586.07    5019 1586.57  5032.2 1592.34    5049 1595.43
  5056.4 1599.72  5093.3 1606.18  5110.6 1609.18  5156.3 1609.82  5215.1 1615.25
  5256.5 1614.97  5296.5 1619.75  5343.6 1619.62  5382.8 1624.87  5446.4 1629.11
  5462.6 1630.96  5501.5 1646.62  5604.1 1668.38  5618.2  1675.6  5637.6 1678.94
  5657.1  1688.8  5685.4 1698.24  5703.1 1699.27    5749 1718.06  5770.1 1730.07
#Mann= 6 ,-1 , 0
  4478.9     .07       0  5001.8     .05       0    5019     .07       0
  5093.3    .035       0  5446.4     .07       0  5462.6      .1       0
Bank Sta=5001.8,5019
XS Rating Curve= 0 ,0
Exp/Cntr=0.3,0.1

Type RM Length L Ch R = 1 ,25699   ,428,428,428
BEGIN DESCRIPTION:
North Creek 49.0
END DESCRIPTION:
XS GIS Cut Line= 3
      1996419.02     13924775.69        1996175.       13924275.
      1996025.01     13923675.05
#Sta/Elev= 30
  4447.3 1619.11  4533.9 1617.54  4616.1 1611.75  4694.6 1612.71  4766.4 1603.45
  4829.7 1602.32  4856.4  1599.3  4939.2 1598.54  4969.9  1590.6  4981.3 1585.19
  4981.8 1584.69  4998.6 1585.19  4999.5 1593.41  5003.3 1601.72  5018.8 1609.85
  5133.3 1613.59    5206 1616.54  5238.3 1621.32  5261.6 1620.95  5281.6 1626.25
  5294.5 1624.92  5358.9 1636.37  5390.2  1649.2  5410.3 1660.04  5464.1 1677.08
  5479.3 1679.93  5507.4    1692    5529 1697.76  5600.1 1737.63  5622.7 1745.37
#Mann= 6 ,-1 , 0
  4447.3     .07       0  4981.3     .05       0  4998.6     .07       0
  5133.3    .035       0  5294.5     .07       0  5410.3      .1       0
Bank Sta=4981.3,4998.6
XS Rating Curve= 0 ,0
Exp/Cntr=0.3,0.1

Type RM Length L Ch R = 1 ,25271   ,450,450,450
BEGIN DESCRIPTION:
North Creek 48.0
END DESCRIPTION:
XS GIS Cut Line= 3
      1996656.19     13924664.92        1996575.       13924175.
      1996225.01     13923625.02
#Sta/Elev= 30
  4499.2 1615.19  4564.7 1608.33  4625.9  1606.1  4720.2 1604.84  4875.2 1607.45
  4908.7 1604.42  4936.1 1594.62  5000.1 1590.92  5011.3  1588.9  5016.9 1584.69
  5017.4 1584.19  5034.2 1584.69  5037.1 1589.23  5050.4 1591.08  5071.7 1598.51
  5151.5 1604.62  5166.5 1605.43    5310 1616.32    5342 1626.16  5372.6 1644.49
  5391.8 1648.17  5427.3    1660  5458.7 1666.28  5493.4  1678.7  5558.9 1698.06
  5583.8 1713.17  5609.1 1725.17  5622.9    1737  5636.8  1743.6  5647.7 1745.86
#Mann= 6 ,-1 , 0
  4499.2     .07       0  5016.9     .05       0  5034.2     .07       0
  5151.5    .035       0  5166.5     .07       0  5372.6      .1       0
Bank Sta=5016.9,5034.2
XS Rating Curve= 0 ,0
Exp/Cntr=0.3,0.1

Type RM Length L Ch R = 1 ,24821   ,668,668,668
BEGIN DESCRIPTION:
North Creek 47.0
END DESCRIPTION:
XS GIS Cut Line= 4
        1996975.     13924624.97        1996975.       13924025.
      1996903.99     13923810.52      1996375.08     13923625.03
#Sta/Elev= 30
  4404.6 1612.05  4558.6 1602.82  4816.7 1598.46  4876.6 1599.22  4915.6 1595.87
  4957.6 1587.94  4975.6 1587.86    4988 1584.49  4988.5 1583.99  5005.3 1584.49
  5005.4 1587.39  5007.7 1588.19    5027 1589.11  5043.6 1590.53  5081.5 1615.31
  5185.8 1619.56  5270.9 1620.52  5310.9 1623.39  5384.1 1632.75  5406.3 1639.26
  5444.5 1643.45  5469.9 1649.19  5487.4 1655.33  5532.7 1656.63  5574.8 1658.14
  5598.1 1670.97  5606.6 1673.73  5657.5 1687.58  5755.1 1708.38    5791 1718.24
#Mann= 6 ,-1 , 0
  4404.6    .035       0    4988    .035       0  5005.3    .035       0
    5027     .07       0  5532.7      .1       0  5755.1     .07       0
Bank Sta=4988,5005.3
XS Rating Curve= 0 ,0
Exp/Cntr=0.3,0.1

Type RM Length L Ch R = 1 ,24153   ,280,280,280
BEGIN DESCRIPTION:
North Creek 46.0
END DESCRIPTION:
XS GIS Cut Line= 4
       1997945.4     13924325.16      1997624.52      13923973.4
      1997548.66     13923882.88      1997046.96     13923648.22
#Sta/Elev= 30
  4526.6 1651.97  4623.2 1644.43  4662.1 1641.98  4691.9 1631.32  4706.9 1628.07
  4713.2 1625.49  4738.6 1609.52  4776.9 1591.84  4791.7  1589.3  4859.2 1587.46
  4881.5 1586.88  4925.5 1582.56  4966.8 1581.52  4974.4 1578.71  5000.2 1576.43
  5000.7 1575.93    5019 1576.43  5054.2 1578.51    5066  1583.6  5073.8 1589.02
  5087.1 1592.84  5290.2 1594.27    5383 1596.14  5459.3 1603.89  5492.4 1604.69
  5518.9  1601.9  5555.3 1603.27  5595.1 1601.46  5626.7  1610.9  5674.7 1613.83
#Mann= 6 ,-1 , 0
  4526.6     .07       0  4623.2      .1       0  4859.2     .07       0
  5000.2     .05       0    5019     .07       0  5290.2    .035       0
Bank Sta=5000.2,5019
XS Rating Curve= 0 ,0
Exp/Cntr=0.3,0.1

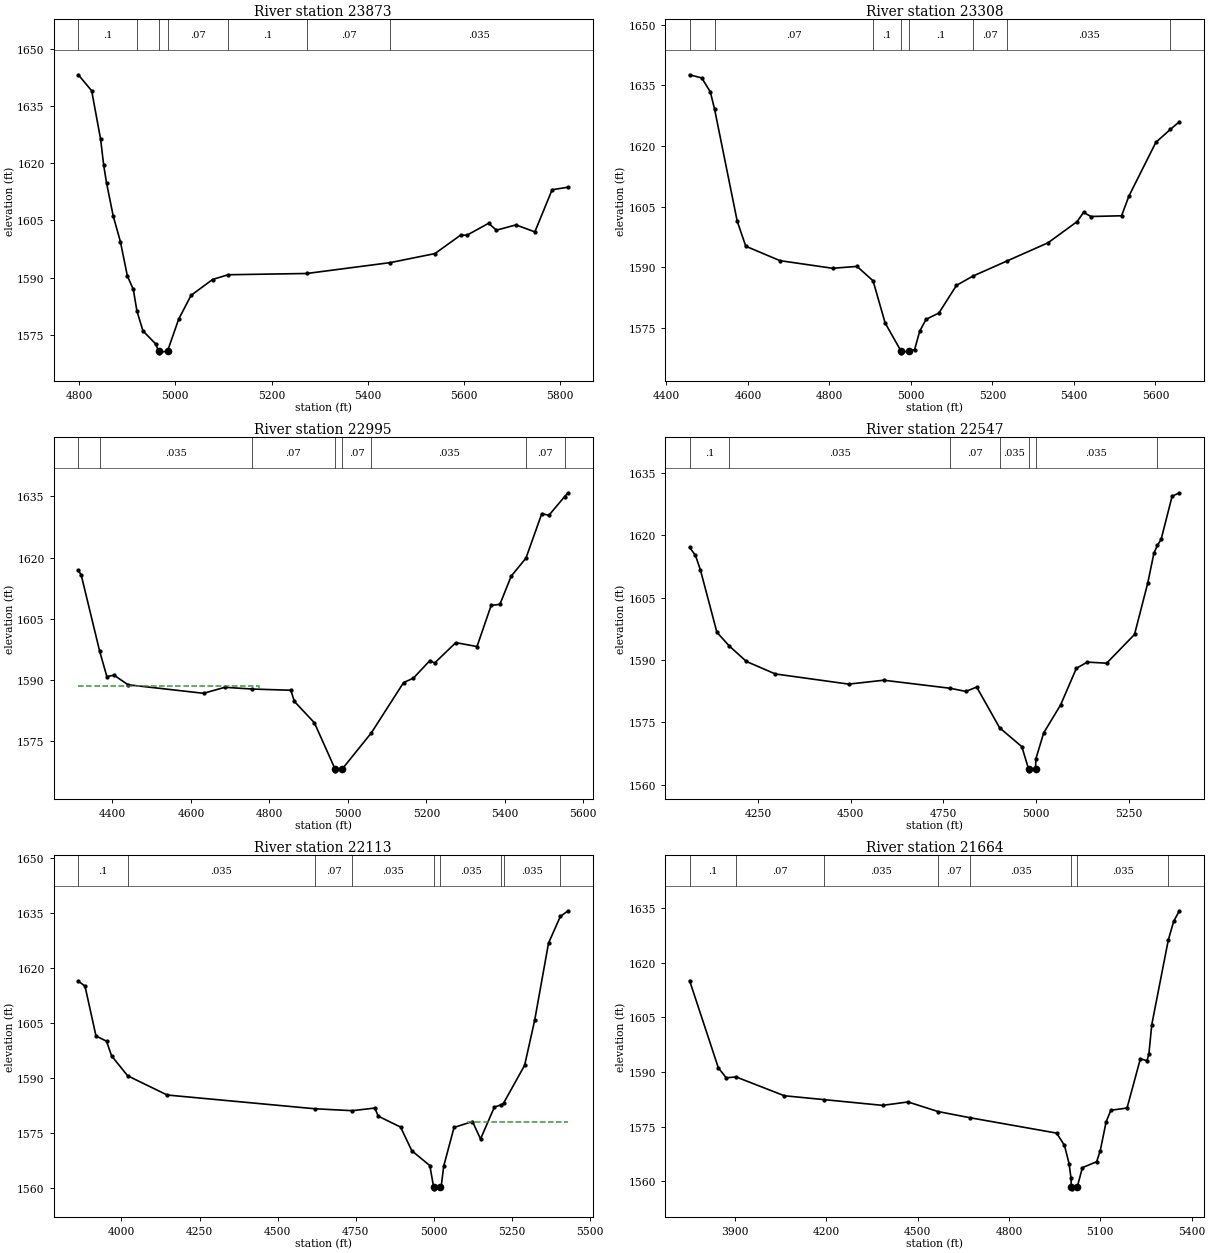
Type RM Length L Ch R = 1 ,23873   ,565,565,565
BEGIN DESCRIPTION:
North Creek 45.0
END DESCRIPTION:
XS GIS Cut Line= 4
      1998024.98     13923874.99        1997825.       13923825.
        1997525.       13923775.      1997058.52     13923573.27
#Sta/Elev= 30
  4798.3 1643.16    4826 1638.97  4844.6 1626.28    4851 1619.47  4856.9 1614.85
  4870.8 1606.16  4885.7 1599.48  4900.2 1590.46  4912.6 1586.93  4920.1 1581.28
  4932.7 1576.05    4959 1572.66    4965 1570.81  4965.5 1570.31  4983.9 1570.81
    5007 1579.15  5032.7 1585.37  5077.4 1589.52  5109.7 1590.77  5273.3  1591.1
  5446.9 1593.95  5539.8 1596.31  5593.9 1601.21    5606  1601.1  5651.6 1604.26
  5667.6 1602.44  5708.3 1603.83  5747.6    1602  5783.5 1613.04  5816.8 1613.71
#Mann= 7 ,-1 , 0
  4798.3      .1       0  4920.1     .07       0    4965     .05       0
  4983.9     .07       0  5109.7      .1       0  5273.3     .07       0
  5446.9    .035       0
Bank Sta=4965,4983.9
XS Rating Curve= 0 ,0
Exp/Cntr=0.3,0.1

Type RM Length L Ch R = 1 ,23308   ,313,313,313
BEGIN DESCRIPTION:
North Creek 44.0
END DESCRIPTION:
XS GIS Cut Line= 4
      1998174.98       13923425.      1997630.52     13923432.46
       1997378.8     13923502.23       1996983.6     13923474.38
#Sta/Elev= 30
  4456.8  1637.6  4486.7 1636.82  4507.7 1633.38  4518.1 1629.13  4573.7 1601.43
  4594.7 1595.25  4678.7 1591.68  4807.7  1589.8  4867.7 1590.26  4907.1  1586.7
  4936.7 1576.29  4975.3 1569.41  4975.8 1568.91  4994.2 1569.41    5009 1569.69
  5021.5 1574.25  5037.2 1577.19  5068.7 1578.75  5111.8 1585.58    5152 1587.86
  5235.2 1591.58  5336.4 1596.09  5407.7 1601.32  5423.6 1603.61  5441.7 1602.59
  5516.9 1602.77  5534.9 1607.63  5601.1 1620.92  5636.9 1624.13  5658.7    1626
#Mann= 8 ,-1 , 0
  4456.8      .1       0  4518.1     .07       0  4907.1      .1       0
  4975.3     .05       0  4994.2      .1       0    5152     .07       0
  5235.2    .035       0  5636.9     .07       0
Bank Sta=4975.3,4994.2
XS Rating Curve= 0 ,0
Exp/Cntr=0.3,0.1

Type RM Length L Ch R = 1 ,22995   ,448,448,448
BEGIN DESCRIPTION:
North Creek 43.0
END DESCRIPTION:
XS GIS Cut Line= 3
       1998160.7     13923134.77        1997475.       13923175.
      1996914.03     13923155.16
#Sta/Elev= 30
  4313.1 1616.92  4320.5 1615.68  4367.4 1597.06  4385.8 1590.82  4403.9 1591.18
  4439.9 1588.82  4632.3 1586.73  4686.4  1588.2  4755.3 1587.78  4854.6 1587.48
  4863.7 1584.74  4914.8 1579.49  4967.1 1568.23  4967.6 1567.73    4986 1568.23
  5059.7 1577.02  5141.9 1589.35    5167 1590.45    5209 1594.75    5221 1594.15
  5275.1 1599.15  5329.1 1598.19  5365.1 1608.26  5387.5 1608.54  5416.2 1615.44
  5453.9 1619.86  5494.2 1630.77  5512.2 1630.34  5552.4 1634.94  5561.3 1635.87
#Mann= 8 ,-1 , 0
  4313.1      .1       0  4367.4    .035       0  4755.3     .07       0
  4967.1     .05       0    4986     .07       0  5059.7    .035       0
  5453.9     .07       0  5552.4    .035       0
#XS Ineff= 2 , 0
         4773.43 1588.58
Permanent Ineff=
       F       F
Bank Sta=4967.1,4986
XS Rating Curve= 0 ,0
Exp/Cntr=0.3,0.1

Type RM Length L Ch R = 1 ,22547   ,434,434,434
BEGIN DESCRIPTION:
North Creek 42.0
END DESCRIPTION:
XS GIS Cut Line= 4
      1998208.65     13923078.63      1997573.28     13922816.38
        1997325.       13922775.      1996975.05     13922924.98
#Sta/Elev= 30
    4066 1617.08  4081.7  1615.2  4095.2 1611.66  4139.7 1596.64  4173.1 1593.34
  4219.2 1589.62    4297 1586.62    4495 1584.17  4589.1 1585.11  4768.2 1583.17
  4810.4 1582.41  4839.7 1583.46  4901.4 1573.66  4961.4  1569.1  4979.3 1563.79
  4979.8 1563.29  4998.2 1563.79  4999.4 1566.25  5020.2 1572.42  5065.9 1579.18
  5108.3 1587.98  5137.7 1589.47  5189.9 1589.21    5265 1596.13  5300.9  1608.6
  5317.2 1615.69  5326.6 1617.55  5336.8 1619.06  5366.2 1629.39  5385.8 1630.24
#Mann= 7 ,-1 , 0
    4066      .1       0  4173.1    .035       0  4768.2     .07       0
  4901.4    .035       0  4979.3    .035       0  4998.2    .035       0
  5326.6     .07       0
Bank Sta=4979.3,4998.2
XS Rating Curve= 0 ,0
Exp/Cntr=0.3,0.1

Type RM Length L Ch R = 1 ,22113   ,449,449,449
BEGIN DESCRIPTION:
North Creek 41.0
END DESCRIPTION:
XS GIS Cut Line= 4
      1998239.14     13923052.78      1997480.77     13922491.82
        1997325.       13922375.      1996975.01     13922125.01
#Sta/Elev= 30
    3862 1616.49  3883.2 1615.17  3918.5 1601.54  3952.2 1600.11  3968.5  1596.1
    4020 1590.66  4146.5 1585.42  4619.2 1581.67    4739 1581.14  4811.1 1581.86
  4822.3 1579.64  4893.6 1576.67  4929.7 1570.21  4987.3 1566.15  4999.5 1560.31
    5000 1559.81  5018.5 1560.31  5024.1 1560.72  5031.8 1566.02  5064.9 1576.57
  5123.9 1578.18  5149.7 1573.42    5194 1582.12  5216.7 1582.78  5223.3 1583.17
  5290.8 1593.53    5323 1605.81  5367.3 1626.87  5405.2 1634.17  5430.1 1635.71
#Mann= 9 ,-1 , 0
    3862      .1       0    4020    .035       0  4619.2     .07       0
    4739    .035       0  4999.5    .035       0  5018.5    .035       0
  5216.7     .07       0  5223.3    .035       0  5405.2     .07       0
#XS Ineff= 2 , 0
                         5109.09         1578.12
Permanent Ineff=
       F       F
Bank Sta=4999.5,5018.5
XS Rating Curve= 0 ,0
Exp/Cntr=0.3,0.1

Type RM Length L Ch R = 1 ,21664   ,422,422,422
BEGIN DESCRIPTION:
North Creek 40.0
END DESCRIPTION:
XS GIS Cut Line= 4
      1998209.12     13922978.92      1997682.37     13922265.31
        1997475.       13921975.      1997125.03     13921875.01
#Sta/Elev= 30
  3751.8 1615.12  3846.2 1591.18    3872 1588.44  3904.5 1588.67  4062.9 1583.51
  4192.8 1582.45  4385.1 1580.87  4468.8 1581.81  4567.6 1579.17  4672.2 1577.48
  4956.5 1573.26  4982.3  1569.9  4997.4 1564.91  5003.7 1560.95  5005.1 1558.46
  5005.6 1557.96  5024.2 1558.46  5041.3 1563.78  5087.9  1565.4  5099.6 1568.33
  5119.1 1576.35  5134.7 1579.53  5187.8 1580.14  5231.5 1593.66  5253.3 1593.13
  5259.5    1595  5268.9 1602.98    5323 1626.18  5340.7 1631.34  5359.5 1634.28
#Mann= 8 ,-1 , 0
  3751.8      .1       0  3904.5     .07       0  4192.8    .035       0
  4567.6     .07       0  4672.2    .035       0  5005.1    .035       0
  5024.2    .035       0    5323     .07       0
Bank Sta=5005.1,5024.2
XS Rating Curve= 0 ,0
Exp/Cntr=0.3,0.1

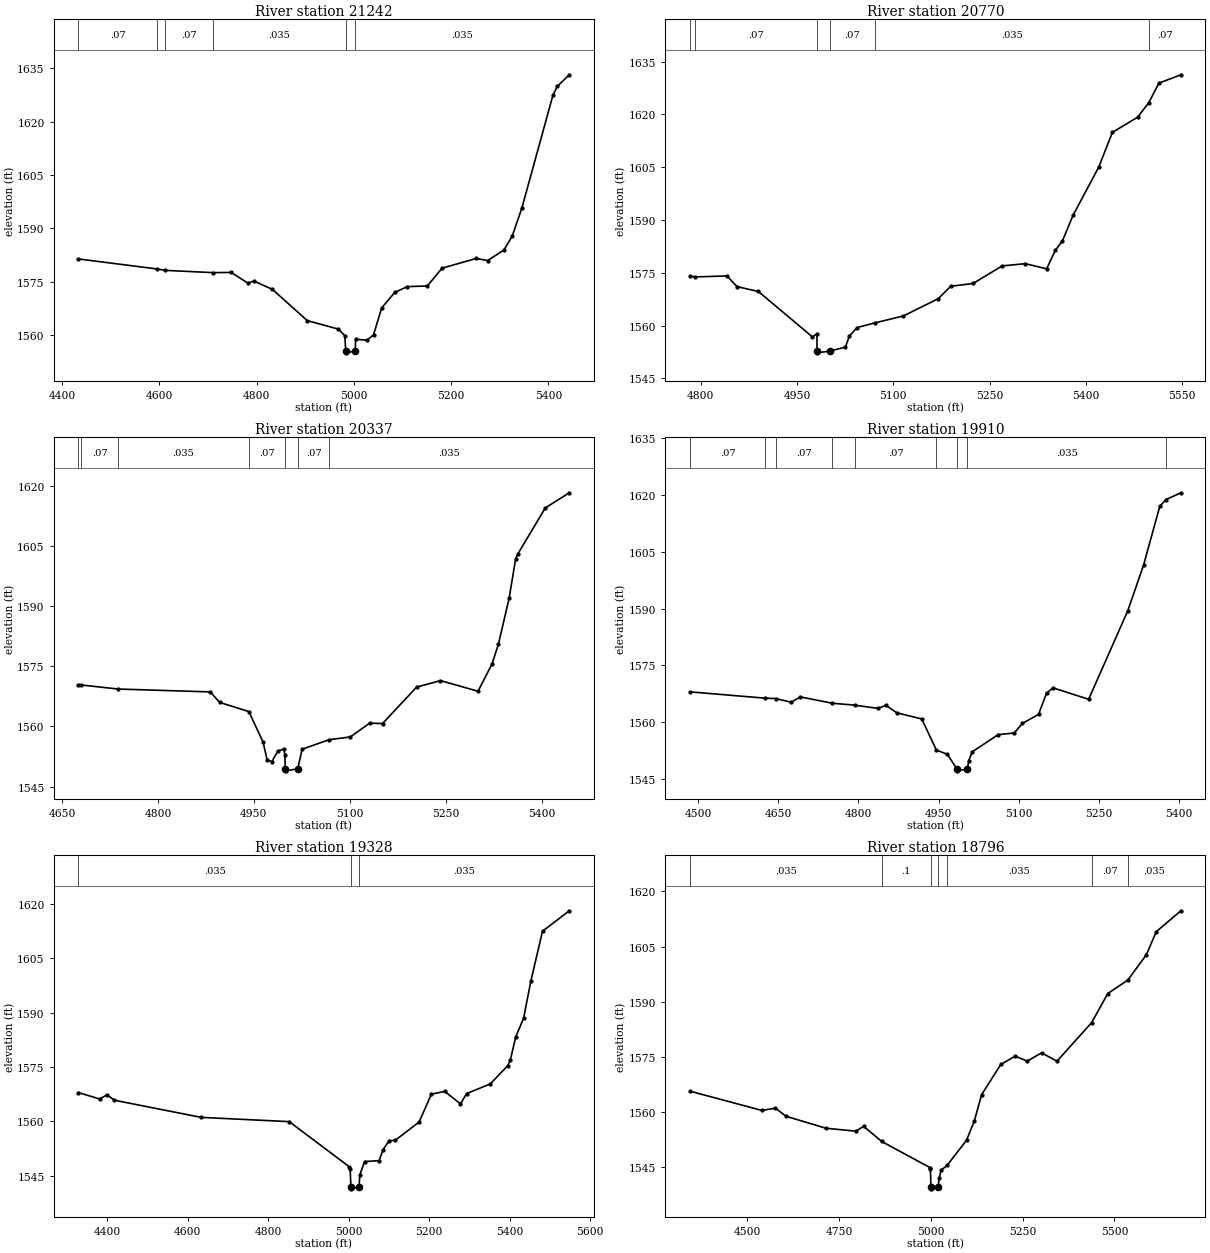
Type RM Length L Ch R = 1 ,21242   ,472,472,472
BEGIN DESCRIPTION:
North Creek 39.0
END DESCRIPTION:
XS GIS Cut Line= 4
       1998232.5     13921678.66      1997833.83     13921663.79
        1997675.       13921625.      1997274.97     13921424.98
#Sta/Elev= 30
  4433.2 1581.43  4594.2 1578.64  4611.8 1578.23  4710.4 1577.59  4747.5 1577.65
  4781.8 1574.65  4793.8 1575.25  4832.2  1572.9  4903.9 1564.13    4968 1561.74
  4981.1  1559.9  4983.1 1555.58  4983.6 1555.08  5002.7 1555.58  5003.3 1558.89
  5026.7 1558.62  5040.2 1560.14    5057 1567.69  5083.8 1572.02  5109.4 1573.67
  5150.9 1573.85  5181.1 1578.84  5251.5 1581.57    5275 1580.98  5308.4 1583.96
  5325.3 1587.77  5345.4 1595.76  5409.2 1627.38    5418 1629.85  5442.9 1633.13
#Mann= 6 ,-1 , 0
  4433.2     .07       0  4594.2    .035       0  4611.8     .07       0
  4710.4    .035       0  4983.1    .035       0  5002.7    .035       0
Bank Sta=4983.1,5002.7
XS Rating Curve= 0 ,0
Exp/Cntr=0.3,0.1

Type RM Length L Ch R = 1 ,20770   ,433,433,433
BEGIN DESCRIPTION:
North Creek 38.0
END DESCRIPTION:
XS GIS Cut Line= 3
        1998025.       13921375.        1997875.       13921225.
        1997325.       13921175.
#Sta/Elev= 30
  4783.4 1574.01  4791.7 1573.82  4841.1  1574.1  4856.6 1571.07  4889.9 1569.68
  4974.1 1556.78  4981.1 1557.67  4981.3 1552.75  4981.8 1552.25  5000.9 1552.75
  5025.5 1553.87  5031.5 1556.99  5043.6 1559.44  5071.1 1560.75  5115.9 1562.74
  5170.1 1567.64  5189.4 1571.16  5224.3 1571.96  5269.5 1576.95  5305.7 1577.58
  5338.8 1576.11  5352.3 1581.37  5363.4 1584.08  5379.9 1591.31  5420.1  1605.1
  5441.2 1614.89  5480.4 1619.19  5497.9 1623.35  5513.5 1628.87  5547.8 1631.25
#Mann= 6 ,-1 , 0
  4783.4    .035       0  4791.7     .07       0  4981.3     .05       0
  5000.9     .07       0  5071.1    .035       0  5497.9     .07       0
Bank Sta=4981.3,5000.9
XS Rating Curve= 0 ,0
Exp/Cntr=0.3,0.1

Type RM Length L Ch R = 1 ,20337   ,427,427,427
BEGIN DESCRIPTION:
North Creek 37.0
END DESCRIPTION:
XS GIS Cut Line= 3
      1998175.01     13921075.01        1997975.       13920825.
      1997574.99     13920624.99
#Sta/Elev= 30
  4675.7 1570.39    4680 1570.34  4737.6 1569.33    4882 1568.61  4896.4    1566
  4942.2 1563.71  4964.3 1556.13  4970.7 1551.72    4978 1551.21  4987.6  1553.9
  4996.8 1554.35  4998.6 1552.83    4999 1549.44  4999.5 1548.94  5018.6 1549.44
  5025.4 1554.33  5067.7  1556.7  5100.8 1557.39    5131 1560.83  5151.1 1560.72
  5204.3 1569.79  5241.7 1571.43  5300.4 1568.78  5322.2 1575.55  5332.2 1580.45
    5349 1591.94  5359.1 1601.69  5362.4 1602.94  5405.5 1614.46  5443.1 1618.24
#Mann= 7 ,-1 , 0
  4675.7    .035       0    4680     .07       0  4737.6    .035       0
  4942.2     .07       0    4999     .05       0  5018.6     .07       0
  5067.7    .035       0
Bank Sta=4999,5018.6
XS Rating Curve= 0 ,0
Exp/Cntr=0.3,0.1

Type RM Length L Ch R = 1 ,19910   ,582,582,582
BEGIN DESCRIPTION:
North Creek 36.0
END DESCRIPTION:
XS GIS Cut Line= 3
      1998425.02     13920675.01        1997975.       13920425.
      1997575.01       13920475.
#Sta/Elev= 30
  4485.1 1567.99  4625.7 1566.32  4645.3 1566.22  4674.7 1565.24  4691.4 1566.66
  4750.9 1564.99  4793.7 1564.47  4836.1 1563.62  4851.8 1564.41  4871.7 1562.47
  4918.5 1560.83  4945.8 1552.63  4966.5 1551.48  4984.2 1547.63  4984.7 1547.13
  5003.9 1547.63  5006.4 1549.86  5012.9 1552.15  5061.2 1556.68  5091.5 1557.12
  5106.6 1559.64  5136.8 1562.03  5151.9 1567.67    5164 1569.04  5230.5 1566.03
  5303.5 1589.31  5333.3 1601.48  5363.6 1616.99  5375.3 1618.77    5403 1620.56
#Mann= 9 ,-1 , 0
  4485.1     .07       0  4625.7    .035       0  4645.3     .07       0
  4750.9    .035       0  4793.7     .07       0  4945.8    .035       0
  4984.2    .035       0  5003.9    .035       0  5375.3     .07       0
Bank Sta=4984.2,5003.9
XS Rating Curve= 0 ,0
Exp/Cntr=0.3,0.1

Type RM Length L Ch R = 1 ,19328   ,532,532,532
BEGIN DESCRIPTION:
North Creek 35.0
END DESCRIPTION:
XS GIS Cut Line= 3
      1998725.03     13920025.01        1998075.       13919875.
      1997524.98       13919825.
#Sta/Elev= 30
  4328.5 1567.97  4381.2  1566.2  4399.6 1567.34  4418.1 1565.85  4633.6 1561.12
  4852.2 1559.95  5000.5 1547.56  5003.5 1546.99  5005.4  1541.9  5005.9  1541.4
  5025.6  1541.9  5027.6 1545.28  5039.4 1548.92  5075.8 1549.19  5084.8 1552.13
  5100.2 1554.66    5115 1554.76  5174.7 1559.83  5205.3 1567.53  5238.5 1568.28
  5277.6 1564.85  5292.7 1567.69  5351.5 1570.34  5395.1  1575.4  5401.2 1576.86
    5415 1583.41  5434.3 1588.47  5452.3 1598.71  5481.3  1612.5  5547.9 1618.14
#Mann= 3 ,-1 , 0
  4328.5    .035       0  5005.4    .035       0  5025.6    .035       0
Bank Sta=5005.4,5025.6
XS Rating Curve= 0 ,0
Exp/Cntr=0.3,0.1

Type RM Length L Ch R = 1 ,18796   ,516,516,516
BEGIN DESCRIPTION:
North Creek 34.0
END DESCRIPTION:
XS GIS Cut Line= 3
      1998724.98     13919724.99        1998175.       13919375.
      1997490.19     13919332.95
#Sta/Elev= 30
  4343.2 1565.63  4539.3 1560.39  4576.3 1561.02  4604.5 1558.82  4713.3 1555.55
  4795.7 1554.74  4816.5 1556.07  4865.8 1551.94  4997.4 1544.83  4998.7 1544.51
  4999.9 1539.55  5000.4 1539.05  5020.1 1539.55    5022 1541.87    5028 1544.14
  5043.8 1545.41  5097.1 1552.29  5118.2 1557.52  5138.2 1564.69  5190.3  1572.9
  5229.4 1575.16  5262.4 1573.81  5301.5 1576.06  5343.6  1573.8  5438.1  1584.3
  5481.9  1592.2  5536.7 1595.88  5587.1 1602.75  5614.1 1609.04  5681.2 1614.73
#Mann= 7 ,-1 , 0
  4343.2    .035       0  4865.8      .1       0  4999.9     .05       0
  5020.1      .1       0  5043.8    .035       0  5438.1     .07       0
  5536.7    .035       0
Bank Sta=4999.9,5020.1
XS Rating Curve= 0 ,0
Exp/Cntr=0.3,0.1