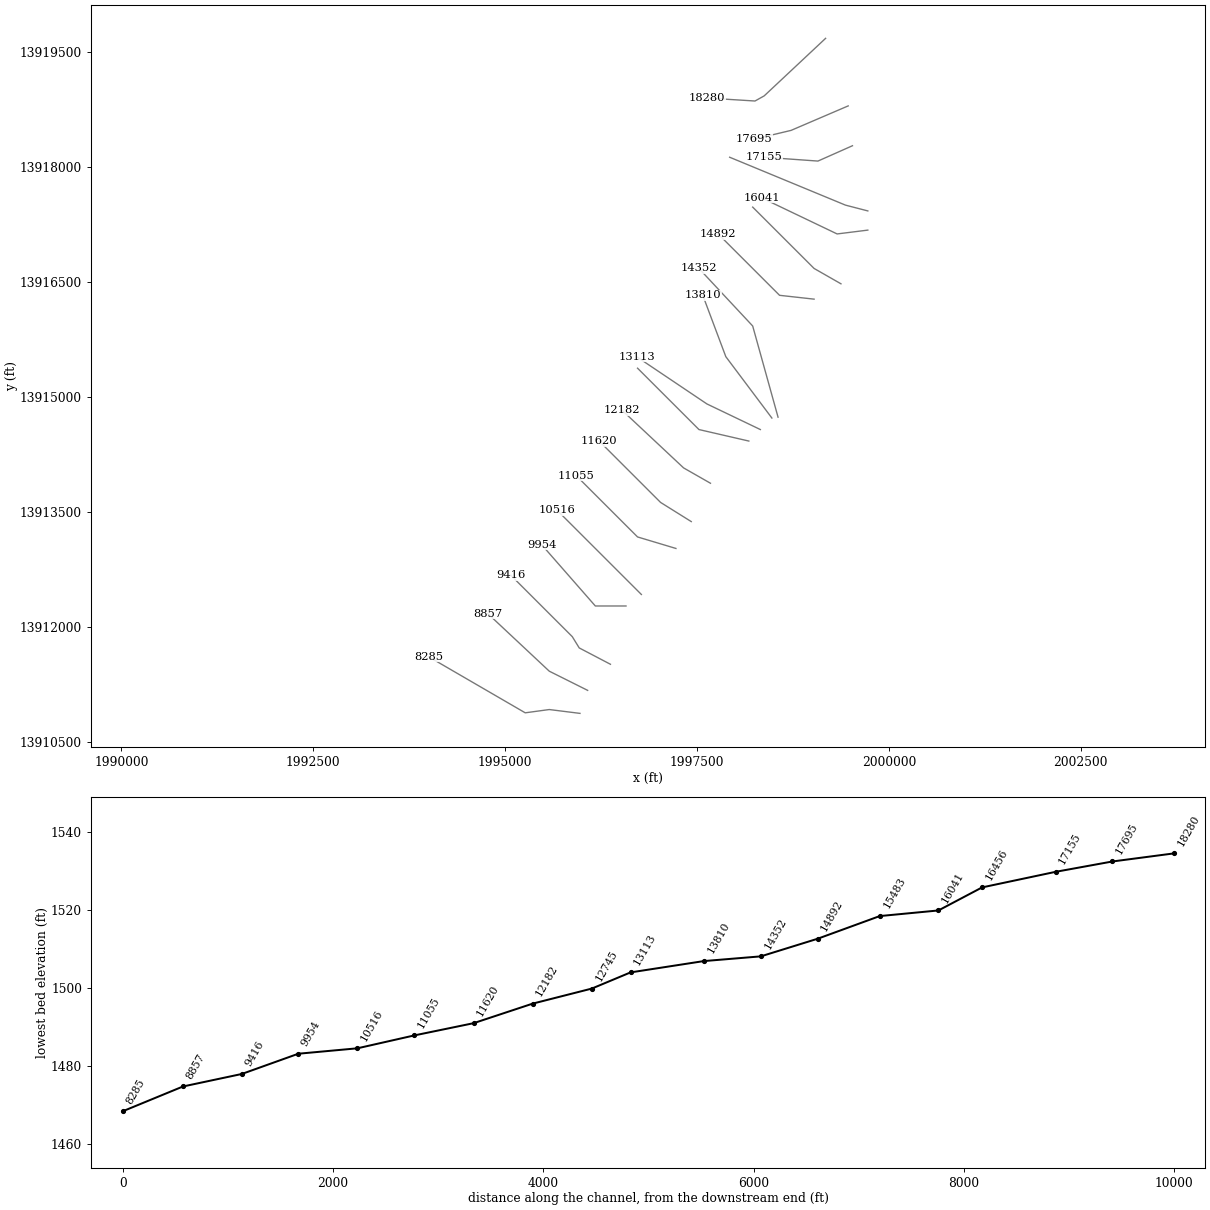
HEC-RAS study North Creek.prj: North Creek Base Level Engineering

--- North Creek.g01 (geometry) --- (continued)

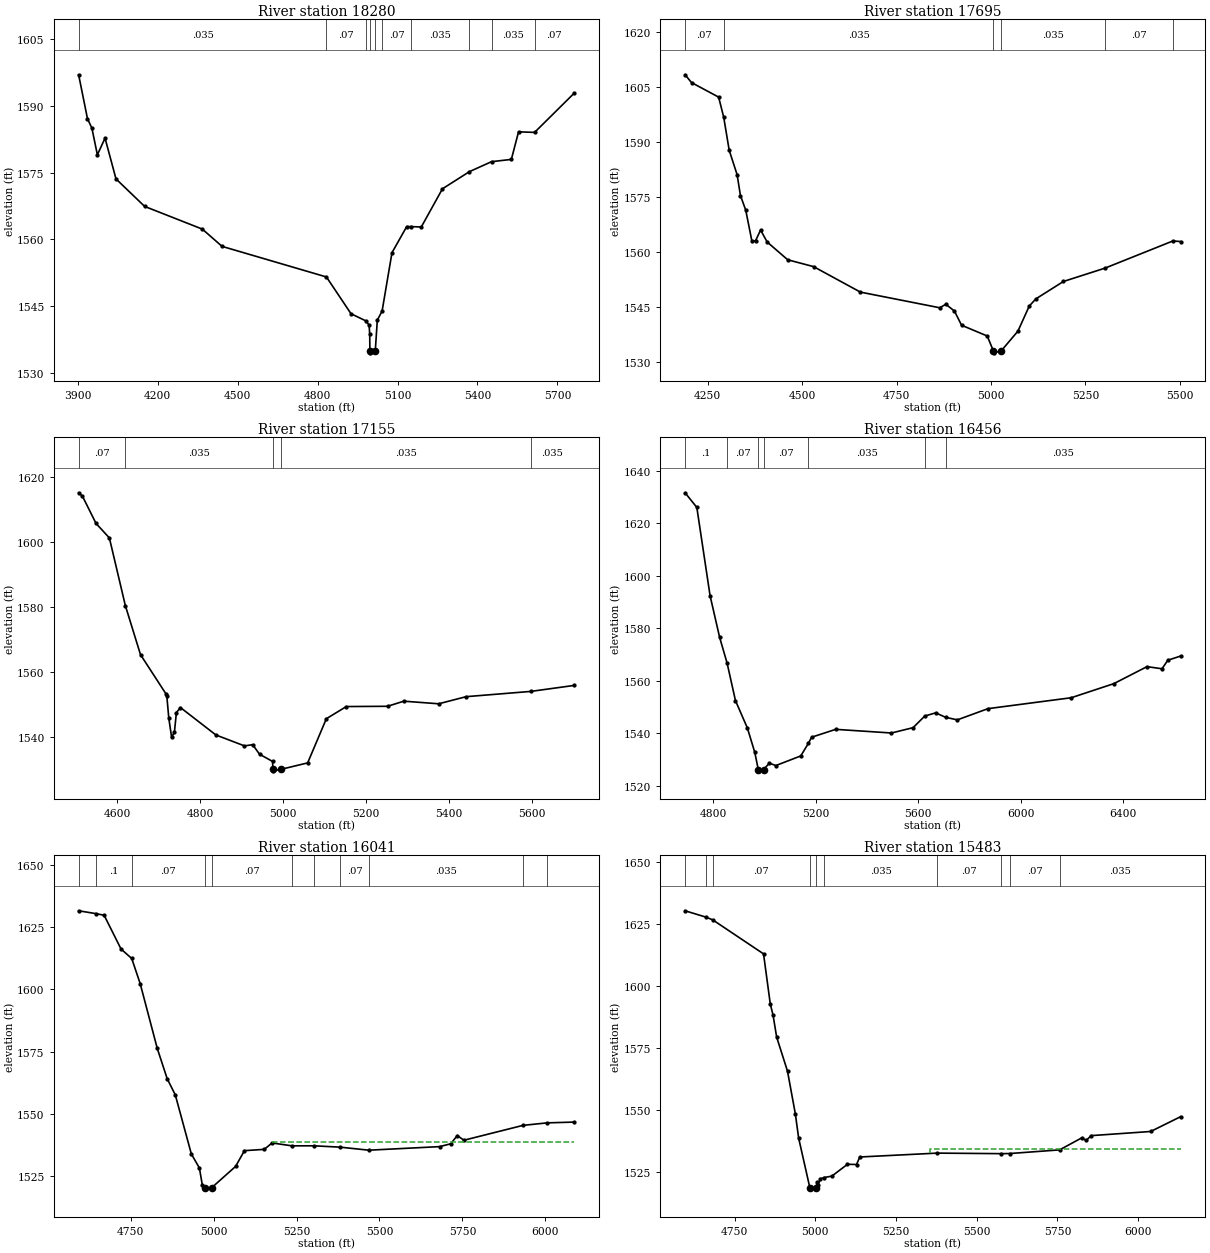
Type RM Length L Ch R = 1 ,18280   ,585,585,585
BEGIN DESCRIPTION:
North Creek 33.0
END DESCRIPTION:
XS GIS Cut Line= 4
      1999175.01     13919675.01        1998375.       13918925.
      1998255.26     13918857.98      1997630.88     13918896.68
#Sta/Elev= 30
  3903.4    1597  3936.5 1587.15  3953.2 1584.98  3973.7    1579  4002.5 1582.75
  4043.6 1573.57  4151.2 1567.38  4367.4 1562.28  4441.7 1558.39  4833.2 1551.51
  4925.6 1543.23    4982 1541.61  4993.4 1540.65  4995.6 1538.69  4996.3 1534.94
  4996.8 1534.44  5016.6 1534.94  5024.1 1541.79  5042.1 1543.84  5079.2 1556.98
  5134.3 1562.83  5151.4 1562.84  5189.2 1562.76  5268.6 1571.35  5369.9 1575.21
  5452.8 1577.45  5527.1 1577.96  5554.1 1584.16  5614.3 1584.04  5762.8 1592.86
#Mann= 10 ,-1 , 0
  3903.4    .035       0  4833.2     .07       0    4982    .035       0
  4996.3    .035       0  5016.6    .035       0  5042.1     .07       0
  5151.4    .035       0  5369.9    .063       0  5452.8    .035       0
  5614.3     .07       0
Bank Sta=4996.3,5016.6
XS Rating Curve= 0 ,0
Exp/Cntr=0.3,0.1

Type RM Length L Ch R = 1 ,17695   ,540,540,540
BEGIN DESCRIPTION:
North Creek 32.0
END DESCRIPTION:
XS GIS Cut Line= 3
      1999469.29     13918794.31        1998725.       13918475.
      1998236.79     13918358.55
#Sta/Elev= 30
  4190.1 1608.32  4207.1 1606.19  4278.9 1602.22  4292.3 1596.72  4306.9 1587.68
  4327.8 1581.03  4336.6 1575.34  4350.7 1571.32    4367 1562.85  4376.8 1563.02
  4389.9 1565.92  4407.4 1562.64  4461.7 1557.79  4530.2 1555.92  4654.1 1548.96
  4864.3 1544.68  4880.3 1545.64  4903.1 1543.78    4922 1539.91  4989.9 1536.97
  5006.3 1532.87  5006.8 1532.37  5026.6 1532.87  5071.2  1538.3  5101.1 1545.14
  5118.5  1547.1  5191.5 1551.86  5301.5  1555.5  5481.5 1562.93  5501.9 1562.77
#Mann= 6 ,-1 , 0
  4190.1     .07       0  4292.3    .035       0  5006.3    .035       0
  5026.6    .035       0  5301.5     .07       0  5481.5    .035       0
Bank Sta=5006.3,5026.6
XS Rating Curve= 0 ,0
Exp/Cntr=0.3,0.1

Type RM Length L Ch R = 1 ,17155   ,699,699,699
BEGIN DESCRIPTION:
North Creek 31.0
END DESCRIPTION:
XS GIS Cut Line= 3
        1999525.       13918275.        1999075.       13918075.
      1998375.02       13918125.
#Sta/Elev= 30
  4507.8 1615.23  4516.9 1614.21  4549.7 1605.81  4581.9 1601.34  4620.4 1580.53
  4656.9 1565.45  4718.3 1553.38  4720.4 1552.59  4725.1 1545.93  4731.9 1539.99
  4738.7 1541.67  4743.4 1547.64  4753.2 1549.18  4838.6 1540.75  4907.5 1537.39
  4927.2 1537.77  4943.7 1534.84  4975.1 1532.61  4976.1 1530.22  4976.6 1529.72
  4996.5 1530.22  5059.7 1532.16  5104.8 1545.75  5152.9 1549.49  5252.2 1549.57
  5291.5 1551.14  5375.5 1550.34  5441.7 1552.53    5597 1554.14    5702 1555.99
#Mann= 5 ,-1 , 0
  4507.8     .07       0  4620.4    .035       0  4976.1     .05       0
  4996.5    .035       0    5597    .035       0
Bank Sta=4976.1,4996.5
XS Rating Curve= 0 ,0
Exp/Cntr=0.3,0.1

Type RM Length L Ch R = 1 ,16456   ,415,415,415
BEGIN DESCRIPTION:
North Creek 30.0
END DESCRIPTION:
XS GIS Cut Line= 3
      1999725.01       13917425.      1999433.67     13917500.68
      1997924.96     13918125.02
#Sta/Elev= 30
  4690.1 1631.61  4735.9 1626.03  4787.5 1592.46  4824.7 1576.61    4854 1566.75
  4886.6 1552.49  4933.2 1542.02    4962 1532.77  4975.7 1526.23  4976.2 1525.73
  4996.2 1526.23  5019.1 1528.66  5044.1 1527.74  5141.5 1531.41    5171 1536.16
  5183.7 1538.53  5277.9 1541.53  5495.4 1540.14  5579.8 1542.17  5625.5  1546.6
    5668 1547.81    5707  1546.1  5752.6 1545.14    5872 1549.41  6196.7 1553.56
  6362.9 1558.92  6492.7 1565.41  6551.2 1564.59  6573.9 1567.85  6623.9 1569.44
#Mann= 7 ,-1 , 0
  4690.1      .1       0    4854     .07       0  4975.7     .05       0
  4996.2     .07       0    5171    .035       0  5625.5     .07       0
    5707    .035       0
Bank Sta=4975.7,4996.2
XS Rating Curve= 0 ,0
Exp/Cntr=0.3,0.1

Type RM Length L Ch R = 1 ,16041   ,558,558,558
BEGIN DESCRIPTION:
North Creek 29.0
END DESCRIPTION:
XS GIS Cut Line= 3
      1999725.01       13917175.        1999325.       13917125.
      1998340.89     13917596.15
#Sta/Elev= 30
  4592.8 1631.55  4643.9 1630.43  4669.7 1629.75  4720.7 1616.17  4752.9 1612.39
  4778.5 1602.24  4829.9 1576.25  4859.8 1564.08  4884.3 1557.57  4932.7 1533.82
  4956.9 1528.22    4966 1521.19  4973.8 1520.33  4974.3 1519.83  4994.4 1520.33
  5066.1 1528.84  5092.7 1535.17  5152.6 1535.69  5175.9 1538.26  5236.2 1537.11
  5302.1 1537.12  5381.3 1536.58  5467.9 1535.36  5681.4 1536.79  5714.7 1537.94
  5734.6 1541.23  5754.6 1539.36  5932.7 1545.33  6005.9 1546.34    6087 1546.65
#Mann= 11 ,-1 , 0
  4592.8    .035       0  4643.9      .1       0  4752.9     .07       0
  4973.8     .05       0  4994.4     .07       0  5236.2     .07       0
  5302.1    .035       0  5381.3     .07       0  5467.9    .035       0
  5932.7     .07       0  6005.9    .035       0
#XS Ineff= 2 , 0
                         5178.62         1538.56
Permanent Ineff=
       F       F
Bank Sta=4973.8,4994.4
XS Rating Curve= 0 ,0
Exp/Cntr=0.3,0.1

Type RM Length L Ch R = 1 ,15483   ,591,591,591
BEGIN DESCRIPTION:
North Creek 28.0
END DESCRIPTION:
XS GIS Cut Line= 3
      1999375.01       13916475.        1999025.       13916675.
      1998224.99     13917475.01
#Sta/Elev= 30
  4596.9 1630.39  4662.5 1627.79  4682.7 1626.71  4839.8 1613.03  4860.6 1592.95
  4869.4 1588.26  4880.4 1579.51    4914 1565.78  4938.2 1548.65  4948.5 1538.84
  4983.1 1518.89  4983.6 1518.39  5003.7 1518.89  5004.7 1521.19  5008.9 1520.12
  5016.1 1522.45  5027.5 1522.95  5051.3 1523.51  5099.7 1528.28  5127.7 1528.19
  5137.9 1531.22  5377.9 1532.78  5576.5 1532.56    5602 1532.61  5756.5 1534.08
  5825.2 1538.92  5839.2  1537.9  5854.1 1539.82  6038.6 1541.49  6131.4 1547.46
#Mann= 10 ,-1 , 0
  4596.9    .035       0  4662.5     .07       0  4682.7     .07       0
  4983.1     .05       0  5003.7     .07       0  5027.5    .035       0
  5377.9     .07       0  5576.5    .035       0    5602     .07       0
  5756.5    .035       0
#XS Ineff= 2 , 0
                         5354.03         1534.59
Permanent Ineff=
       F       F
Bank Sta=4983.1,5003.7
XS Rating Curve= 0 ,0
Exp/Cntr=0.3,0.1

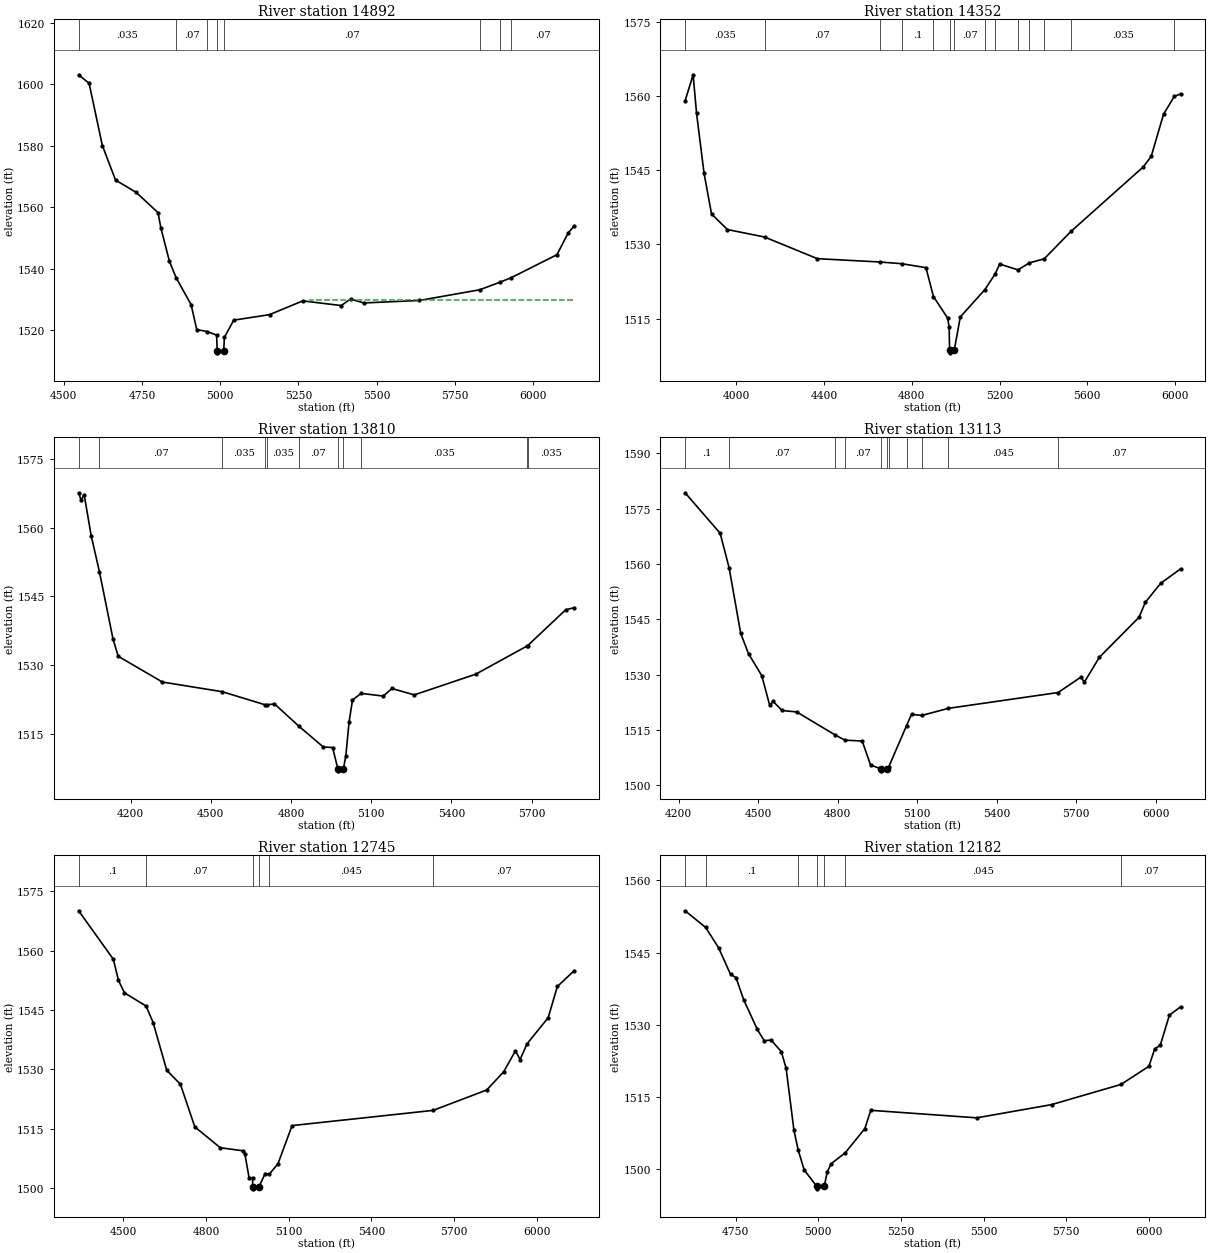
Type RM Length L Ch R = 1 ,14892   ,540,540,540
BEGIN DESCRIPTION:
North Creek 27.0
END DESCRIPTION:
XS GIS Cut Line= 3
      1999025.02       13916275.        1998575.       13916325.
      1997774.97     13917125.03
#Sta/Elev= 30
  4547.2 1603.15  4580.7 1600.37    4623 1580.11  4665.2 1568.85  4731.6 1564.81
  4801.1 1558.23  4810.1 1553.26  4837.3 1542.46  4858.5 1537.11  4906.7 1528.29
  4924.8 1520.16  4958.1 1519.52  4988.2 1518.36  4990.4 1513.08  4990.9 1512.58
    5011 1513.08  5013.1  1517.6  5043.1 1523.23  5157.4 1525.02  5263.7  1529.5
  5386.8 1527.98  5416.5 1530.11  5458.9 1528.83  5636.7 1529.64  5829.4 1533.12
  5892.7 1535.53    5931  1537.1  6076.3 1544.54  6112.8 1551.74  6131.4 1553.88
#Mann= 8 ,-1 , 0
  4547.2    .035       0  4858.5     .07       0  4958.1     .07       0
  4990.4     .05       0    5011     .07       0  5829.4     .07       0
  5892.7    .035       0    5931     .07       0
#XS Ineff= 2 , 0
                         5285.89         1529.92
Permanent Ineff=
       F       F
Bank Sta=4990.4,5011
XS Rating Curve= 0 ,0
Exp/Cntr=0.3,0.1

Type RM Length L Ch R = 1 ,14352   ,542,542,542
BEGIN DESCRIPTION:
North Creek 26.0
END DESCRIPTION:
XS GIS Cut Line= 3
      1998555.39     13914736.28        1998225.       13915925.
      1997524.99     13916675.01
#Sta/Elev= 30
  3766.2 1559.05  3802.8 1564.32  3818.3 1556.59  3852.6 1544.41  3886.8 1536.15
  3959.4 1533.01  4128.5  1531.5  4369.4 1527.12  4653.3 1526.45  4754.5  1526.1
  4864.5  1525.3  4898.7 1519.46  4963.3 1515.11  4970.4 1513.28  4972.2 1508.57
  4972.7 1508.07  4993.5 1508.57  5021.1 1515.33  5133.4 1520.87  5180.3 1524.06
  5200.5 1526.03  5284.1 1524.86  5336.5 1526.27  5403.7 1527.09  5526.7 1532.67
  5855.2 1545.67  5891.5  1547.8    5948 1556.33  5996.9 1559.95  6025.9 1560.46
#Mann= 14 ,-1 , 0
  3766.2    .035       0  4128.5     .07       0  4653.3    .035       0
  4754.5      .1       0  4898.7     .07       0  4972.2     .05       0
  4993.5     .07       0  5133.4     .07       0  5180.3    .035       0
  5284.1     .07       0  5336.5    .035       0  5403.7     .07       0
  5526.7    .035       0  5996.9     .07       0
#XS Ineff= 2 , 0
                          5202.3         1525.99
Permanent Ineff=
       F       F
Bank Sta=4972.2,4993.5
XS Rating Curve= 0 ,0
Exp/Cntr=0.3,0.1

Type RM Length L Ch R = 1 ,13810   ,697,697,697
BEGIN DESCRIPTION:
North Creek 25.0
END DESCRIPTION:
XS GIS Cut Line= 3
      1998475.02     13914724.97        1997875.       13915525.
      1997575.01     13916324.96
#Sta/Elev= 30
  4005.2 1567.67  4014.6 1566.03  4025.9 1567.28  4052.1 1558.31  4083.1 1550.38
  4134.1 1535.63  4153.4 1531.91  4318.7 1526.28  4542.3 1524.17  4703.3  1521.3
  4708.5 1521.28    4738 1521.51  4828.6 1516.66    4921 1512.07  4955.5 1511.96
  4974.9 1507.36  4975.4 1506.86  4996.2 1507.36    5005 1510.09  5017.2 1517.52
    5030 1522.35  5062.2  1523.8  5145.4 1523.21  5177.4 1524.87  5261.1 1523.47
  5491.4    1528  5683.6 1534.17  5685.2 1534.22  5827.8 1542.08  5859.6 1542.54
#Mann= 11 ,-1 , 0
  4005.2      .1       0  4083.1     .07       0  4542.3    .035       0
  4703.3     .07       0  4708.5    .035       0  4828.6     .07       0
  4974.9     .05       0  4996.2     .07       0  5062.2    .035       0
  5683.6     .07       0  5685.2    .035       0
Bank Sta=4974.9,4996.2
XS Rating Curve= 0 ,0
Exp/Cntr=0.3,0.1

Type RM Length L Ch R = 1 ,13113   ,368,368,368
BEGIN DESCRIPTION:
North Creek 24.0
END DESCRIPTION:
XS GIS Cut Line= 3
      1998324.99     13914575.01      1997628.71     13914908.84
      1996717.34     13915521.81
#Sta/Elev= 30
  4224.2 1579.32  4356.5 1568.35  4390.4 1558.97  4434.1 1541.21  4463.6  1535.7
  4513.5 1529.78  4543.4 1521.76  4556.7 1522.77    4590 1520.32  4645.5 1519.92
  4790.2  1513.7  4827.8 1512.28  4892.7 1512.03  4924.3 1505.55  4964.7 1504.46
  4965.2 1503.96  4987.1 1504.46    4992  1504.9  5060.3 1516.24    5079  1519.3
  5116.9 1518.96  5218.2  1520.9  5631.9 1525.18  5718.3 1529.36  5731.3 1527.99
  5787.6  1534.7  5937.8  1545.6  5961.2  1549.6    6019 1554.77  6094.7  1558.7
#Mann= 11 ,-1 , 0
  4224.2      .1       0  4390.4     .07       0  4790.2    .035       0
  4827.8     .07       0  4964.7     .05       0  4987.1     .07       0
    4992    .035       0  5060.3     .07       0  5116.9    .035       0
  5218.2    .045       0  5631.9     .07       0
Bank Sta=4964.7,4987.1
XS Rating Curve= 0 ,0
Exp/Cntr=0.3,0.1

Type RM Length L Ch R = 1 ,12745   ,563,563,563
BEGIN DESCRIPTION:
North Creek 23.0
END DESCRIPTION:
XS GIS Cut Line= 3
      1998174.97     13914425.01        1997525.       13914575.
      1996725.01     13915374.99
#Sta/Elev= 30
  4337.6 1570.08  4463.5 1557.84  4482.1 1552.52  4503.7 1549.36  4582.6    1546
  4607.9 1541.84  4657.6 1529.73  4706.9 1526.26  4759.2 1515.48  4851.6 1510.21
  4934.7 1509.43  4940.9 1508.67  4956.3 1502.59  4968.6 1502.64  4969.6 1500.32
  4970.1 1499.82  4992.1 1500.32  5014.3 1503.67  5029.6 1503.52    5061 1506.15
  5112.2  1515.8  5623.9 1519.64  5818.6  1524.8  5880.4 1529.42  5922.8 1534.69
  5939.8  1532.5  5964.7 1536.44  6041.6 1543.06    6075 1550.95    6136 1554.94
#Mann= 6 ,-1 , 0
  4337.6      .1       0  4582.6     .07       0  4969.6     .05       0
  4992.1     .07       0  5029.6    .045       0  5623.9     .07       0
Bank Sta=4969.6,4992.1
XS Rating Curve= 0 ,0
Exp/Cntr=0.3,0.1

Type RM Length L Ch R = 1 ,12182   ,562,562,562
BEGIN DESCRIPTION:
North Creek 22.0
END DESCRIPTION:
XS GIS Cut Line= 3
      1997675.04     13913874.98        1997325.       13914075.
      1996525.03     13914824.97
#Sta/Elev= 30
  4596.9 1553.68  4659.1 1550.22    4698 1546.03  4734.5 1540.47  4750.9 1539.82
  4774.1 1535.23  4815.6 1529.04  4836.3 1526.72  4857.1 1526.84  4888.2 1524.43
  4902.6 1520.99  4926.2 1508.17  4938.9 1504.08  4957.3 1499.88  4995.5 1496.46
    4996 1495.96    5018 1496.46  5027.3 1499.55  5039.6 1501.21  5081.4 1503.43
  5140.8 1508.46  5158.9 1512.26  5479.6  1510.7  5705.8 1513.44  5915.9 1517.63
  6000.5 1521.39  6018.3 1525.05  6034.8 1525.74  6062.7 1532.02  6096.6 1533.75
#Mann= 7 ,-1 , 0
  4596.9     .07       0  4659.1      .1       0  4938.9     .07       0
  4995.5     .05       0    5018     .07       0  5081.4    .045       0
  5915.9     .07       0
Bank Sta=4995.5,5018
XS Rating Curve= 0 ,0
Exp/Cntr=0.3,0.1

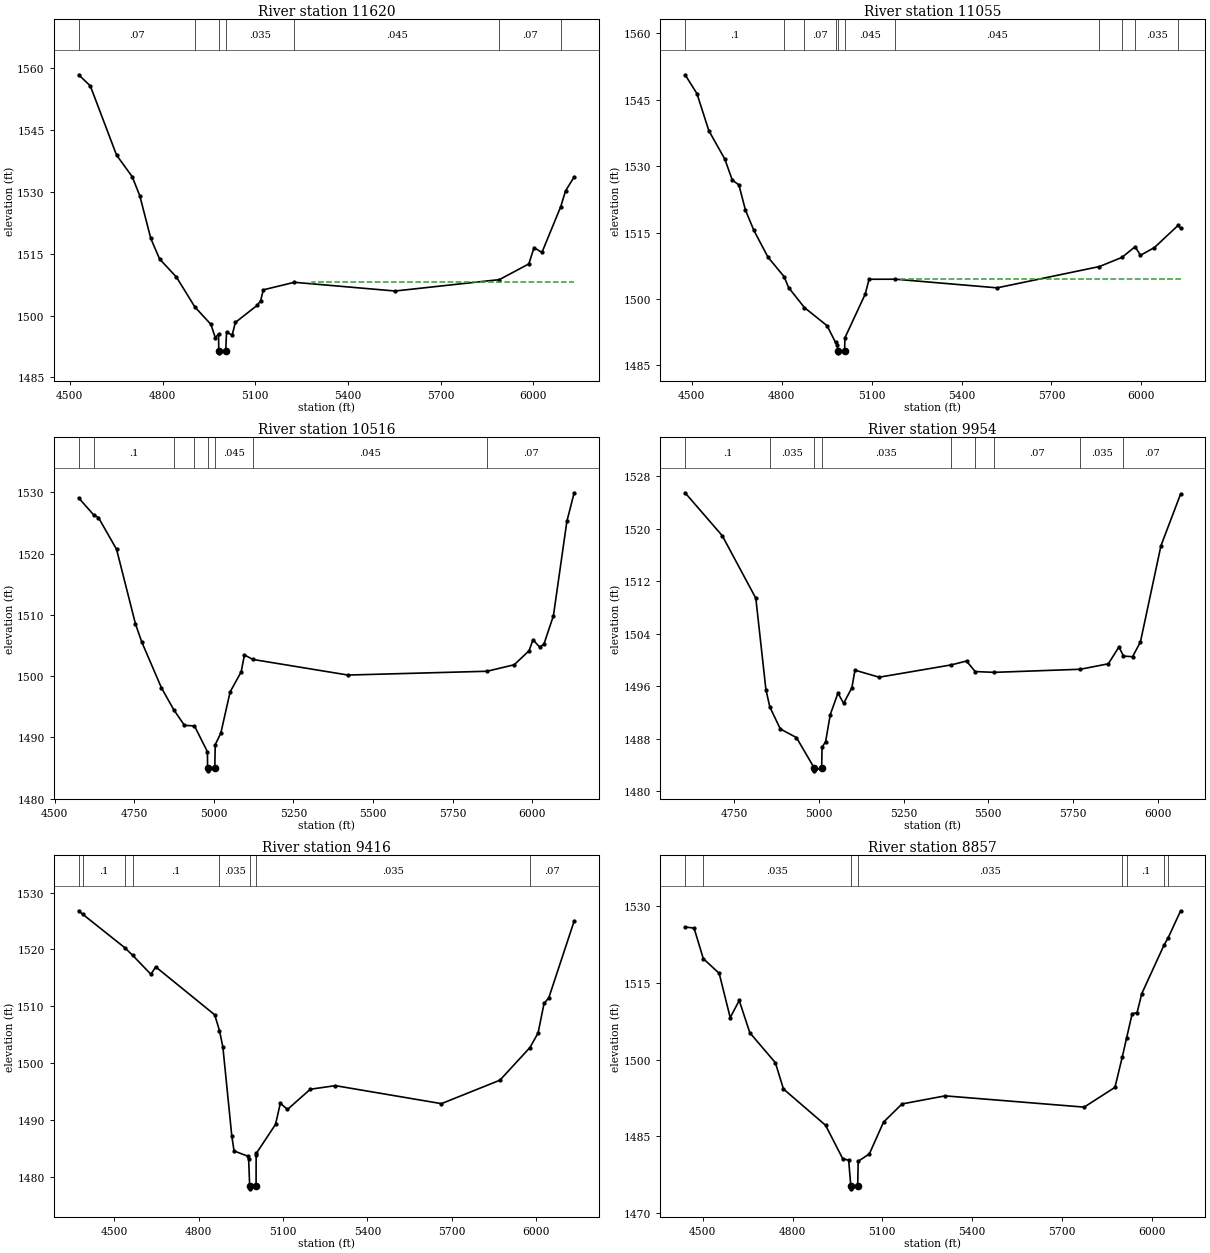
Type RM Length L Ch R = 1 ,11620   ,565,565,565
BEGIN DESCRIPTION:
North Creek 21.0
END DESCRIPTION:
XS GIS Cut Line= 3
      1997425.03     13913374.98        1997025.       13913625.
        1996225.       13914425.
#Sta/Elev= 30
  4528.5  1558.4  4566.3  1555.7  4651.2 1538.91  4701.7  1533.7  4726.5 1529.02
  4761.9  1518.7  4790.6 1513.69    4845 1509.32  4904.2 1502.11  4956.4 1497.85
  4970.6 1494.64  4981.2 1495.51  4981.8 1491.45  4982.3 1490.95  5004.3 1491.45
  5007.1 1496.04    5025 1495.21  5035.6 1498.33  5106.6  1502.5  5117.4 1503.61
  5125.9 1506.23  5226.3 1508.06  5552.1 1505.95  5889.6 1508.71  5984.9 1512.52
  6001.8 1516.47  6027.3  1515.3  6088.2 1526.42  6103.6 1530.22  6131.6 1533.63
#Mann= 7 ,-1 , 0
  4528.5     .07       0  4904.2    .035       0  4981.8     .05       0
  5004.3    .035       0  5226.3    .045       0  5889.6     .07       0
  6088.2    .035       0
#XS Ineff= 2 , 0
                         5284.72         1508.02
Permanent Ineff=
       F       F
Bank Sta=4981.8,5004.3
XS Rating Curve= 0 ,0
Exp/Cntr=0.3,0.1

Type RM Length L Ch R = 1 ,11055   ,539,539,539
BEGIN DESCRIPTION:
North Creek 20.0
END DESCRIPTION:
XS GIS Cut Line= 3
      1997225.04     13913024.99        1996725.       13913175.
      1995925.02     13913974.98
#Sta/Elev= 30
  4477.7 1550.65  4517.2  1546.4  4556.9 1538.02  4610.2 1531.59  4635.1 1526.86
  4657.2 1525.76  4679.1 1520.06  4707.3 1515.47  4754.3 1509.43  4808.1 1505.02
  4823.1 1502.56  4875.7 1498.05  4951.6 1493.93  4979.6 1490.17    4986 1489.49
  4987.3 1488.31  4987.8 1487.81  5009.9 1488.31  5010.9  1491.2  5078.7 1501.08
  5091.5 1504.44  5179.5 1504.45  5518.8  1502.5  5860.1 1507.31  5935.2 1509.38
  5979.3  1511.8  5997.1 1509.85  6043.8 1511.61  6123.3 1516.66  6131.1 1515.93
#Mann= 11 ,-1 , 0
  4477.7      .1       0  4808.1    .035       0  4875.7     .07       0
  4979.6    .045       0  4987.3     .05       0  5009.9    .045       0
  5179.5    .045       0  5860.1     .07       0  5935.2    .045       0
  5979.3    .035       0  6123.3     .07       0
#XS Ineff= 2 , 0
                          5196.6         1504.43
Permanent Ineff=
       F       F
Bank Sta=4987.3,5009.9
XS Rating Curve= 0 ,0
Exp/Cntr=0.3,0.1

Type RM Length L Ch R = 1 ,10516   ,562,562,562
BEGIN DESCRIPTION:
North Creek 19.0
END DESCRIPTION:
XS GIS Cut Line= 3
      1996775.01     13912424.99        1996475.       13912725.
      1995675.03     13913524.97
#Sta/Elev= 30
  4575.7 1529.12  4622.4 1526.37    4638 1525.89  4694.8 1520.71  4754.2 1508.51
  4773.8 1505.58  4835.7 1498.08  4874.2 1494.51  4907.8 1491.96  4939.4 1491.85
    4980 1487.64  4980.5 1485.02    4981 1484.52  5003.2 1485.02  5004.5  1488.8
    5022 1490.66  5051.2 1497.41    5086 1500.69  5096.2 1503.46  5122.6 1502.72
  5421.2 1500.17  5857.7 1500.79    5943 1501.85  5989.7 1504.14    6002 1505.93
  6023.2 1504.73  6036.4 1505.23  6066.1 1509.85  6108.5 1525.31  6131.3 1529.95
#Mann= 8 ,-1 , 0
  4575.7     .07       0  4622.4      .1       0  4874.2     .07       0
  4939.4    .045       0  4980.5     .05       0  5003.2    .045       0
  5122.6    .045       0  5857.7     .07       0
Bank Sta=4980.5,5003.2
XS Rating Curve= 0 ,0
Exp/Cntr=0.3,0.1

Type RM Length L Ch R = 1 ,9954    ,538,538,538
BEGIN DESCRIPTION:
North Creek 18.0
END DESCRIPTION:
XS GIS Cut Line= 3
      1996574.96       13912275.        1996175.       13912275.
      1995474.98     13913075.02
#Sta/Elev= 30
  4604.8 1525.45  4714.6 1518.91  4813.6  1509.4  4843.4 1495.49  4854.9 1492.86
  4885.8 1489.51  4933.6 1488.19  4985.3 1483.63  4985.8 1483.13    5008 1483.63
  5009.1 1486.71  5019.7 1487.58  5033.4  1491.7  5056.2 1494.97  5072.8  1493.4
  5097.2 1495.78  5106.3 1498.45  5177.7 1497.38  5390.2 1499.25  5435.6 1499.84
  5461.1 1498.24  5517.4 1498.12  5771.7 1498.59  5854.2 1499.42  5885.7 1501.99
  5899.1 1500.59  5925.9  1500.5  5949.1 1502.75  6009.6 1517.38  6067.8 1525.28
#Mann= 9 ,-1 , 0
  4604.8      .1       0  4854.9    .035       0  4985.3    .035       0
    5008    .035       0  5390.2     .07       0  5461.1    .035       0
  5517.4     .07       0  5771.7    .035       0  5899.1     .07       0
Bank Sta=4985.3,5008
XS Rating Curve= 0 ,0
Exp/Cntr=0.3,0.1

Type RM Length L Ch R = 1 ,9416    ,559,559,559
BEGIN DESCRIPTION:
North Creek 17.0
END DESCRIPTION:
XS GIS Cut Line= 4
      1996371.94     13911515.09      1995965.24     13911728.18
        1995875.       13911875.      1995074.97     13912675.03
#Sta/Elev= 30
  4372.8  1526.8  4386.6 1526.22  4536.5 1520.33  4564.5    1519    4630 1515.64
  4646.9 1516.95  4856.9 1508.52  4873.9 1505.74    4886 1502.83  4917.7 1487.23
  4925.7  1484.6    4974 1483.69  4977.6 1483.18  4981.3 1478.44  4981.8 1477.94
  5004.1 1478.44  5004.3 1483.94  5005.5 1484.21  5073.4 1489.28  5090.3 1492.98
  5115.8 1491.89  5196.9 1495.44    5286 1496.07  5663.4 1492.91  5871.5 1497.03
  5978.4 1502.77  6007.3 1505.32  6028.5 1510.51  6045.5 1511.52  6135.7    1525
#Mann= 8 ,-1 , 0
  4372.8     .07       0  4386.6      .1       0  4536.5     .07       0
  4564.5      .1       0  4873.9    .035       0  4981.3    .035       0
  5004.1    .035       0  5978.4     .07       0
Bank Sta=4981.3,5004.1
XS Rating Curve= 0 ,0
Exp/Cntr=0.3,0.1

Type RM Length L Ch R = 1 ,8857    ,572,572,572
BEGIN DESCRIPTION:
North Creek 16.0
END DESCRIPTION:
XS GIS Cut Line= 3
      1996074.98     13911175.01        1995575.       13911425.
      1994774.99     13912175.01
#Sta/Elev= 30
    4441 1525.89    4471 1525.66  4501.8  1519.7  4554.9 1516.83  4591.7 1508.18
  4621.9 1511.53  4657.2 1505.23  4742.7 1499.37  4769.5 1494.25  4910.4 1487.15
  4967.4 1480.65  4987.5 1480.32  4994.7 1475.24  4995.2 1474.74  5017.6 1475.24
  5019.3 1480.11  5056.7 1481.58    5104 1487.77  5165.7 1491.32  5309.6  1492.9
  5774.3  1490.7  5877.1 1494.56  5901.9 1500.56  5916.2 1504.25  5934.6 1508.93
  5951.1 1509.16  5966.8 1512.88    6041 1522.33  6055.4 1523.83  6096.6 1529.05
#Mann= 8 ,-1 , 0
    4441     .07       0  4501.8    .035       0  4994.7    .035       0
  5017.6    .035       0  5901.9     .07       0  5916.2      .1       0
    6041     .07       0  6055.4    .035       0
Bank Sta=4994.7,5017.6
XS Rating Curve= 0 ,0
Exp/Cntr=0.3,0.1

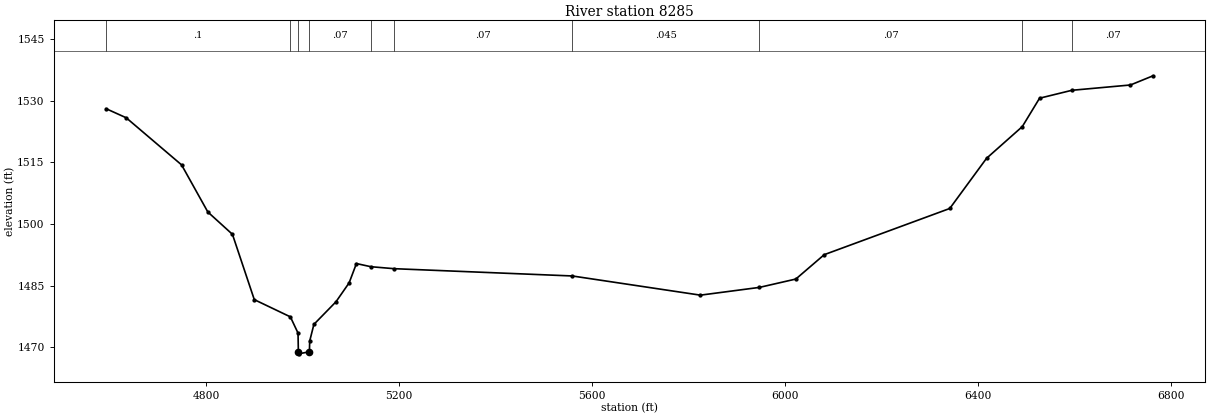
Type RM Length L Ch R = 1 ,8285    ,545,545,545
BEGIN DESCRIPTION:
North Creek 15.0
END DESCRIPTION:
XS GIS Cut Line= 4
      1995974.99       13910875.        1995575.       13910925.
       1995261.8     13910882.26      1994006.58     13911611.52
#Sta/Elev= 30
  4592.4 1528.04  4633.9 1525.84  4748.7 1514.38  4803.2 1502.91  4854.2 1497.48
  4899.5 1481.59  4974.3  1477.4  4990.2 1473.45  4990.9  1468.9  4991.4  1468.4
  5013.8  1468.9  5014.4 1471.51  5023.1 1475.57  5068.9 1481.07  5096.2 1485.68
  5111.3 1490.37  5141.2  1489.6  5189.6 1489.12  5558.8 1487.35  5824.6 1482.68
  5947.1 1484.57  6022.5  1486.6  6081.4 1492.53  6341.7 1503.77    6418 1515.98
  6492.1 1523.69  6527.9  1530.6    6595 1532.53  6716.4 1533.82  6763.3 1536.06
#Mann= 10 ,-1 , 0
  4592.4      .1       0  4974.3     .07       0  4990.9     .05       0
  5013.8     .07       0  5141.2    .045       0  5189.6     .07       0
  5558.8    .045       0  5947.1     .07       0  6492.1      .1       0
    6595     .07       0
Bank Sta=4990.9,5013.8
XS Rating Curve= 0 ,0
Exp/Cntr=0.3,0.1