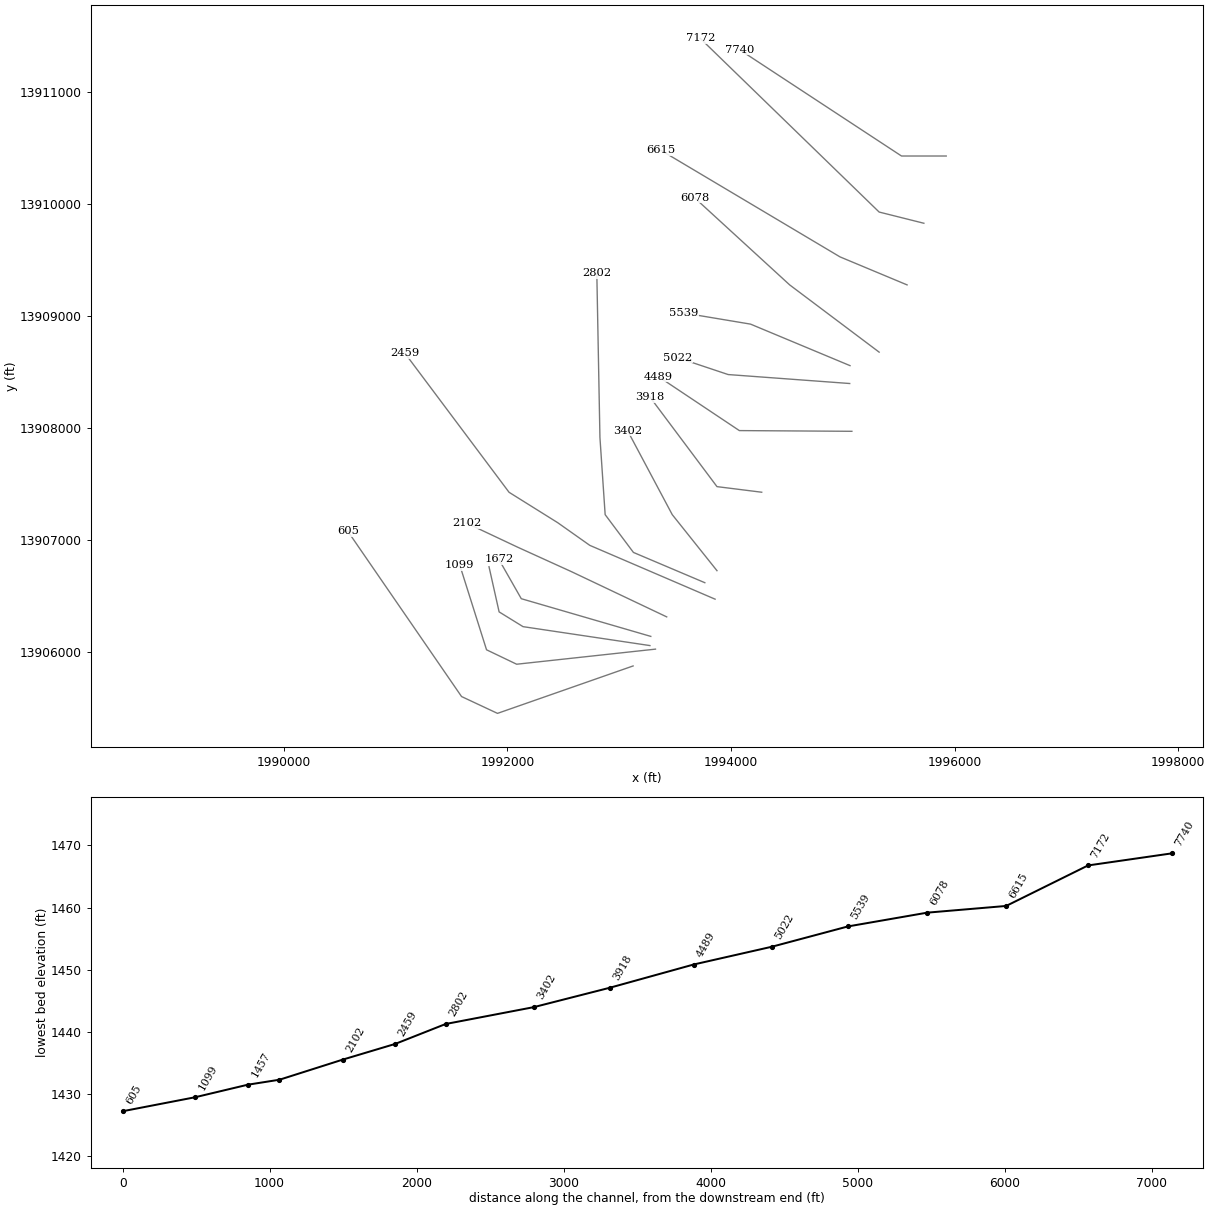
HEC-RAS study North Creek.prj: North Creek Base Level Engineering

--- North Creek.g01 (geometry) --- (continued)

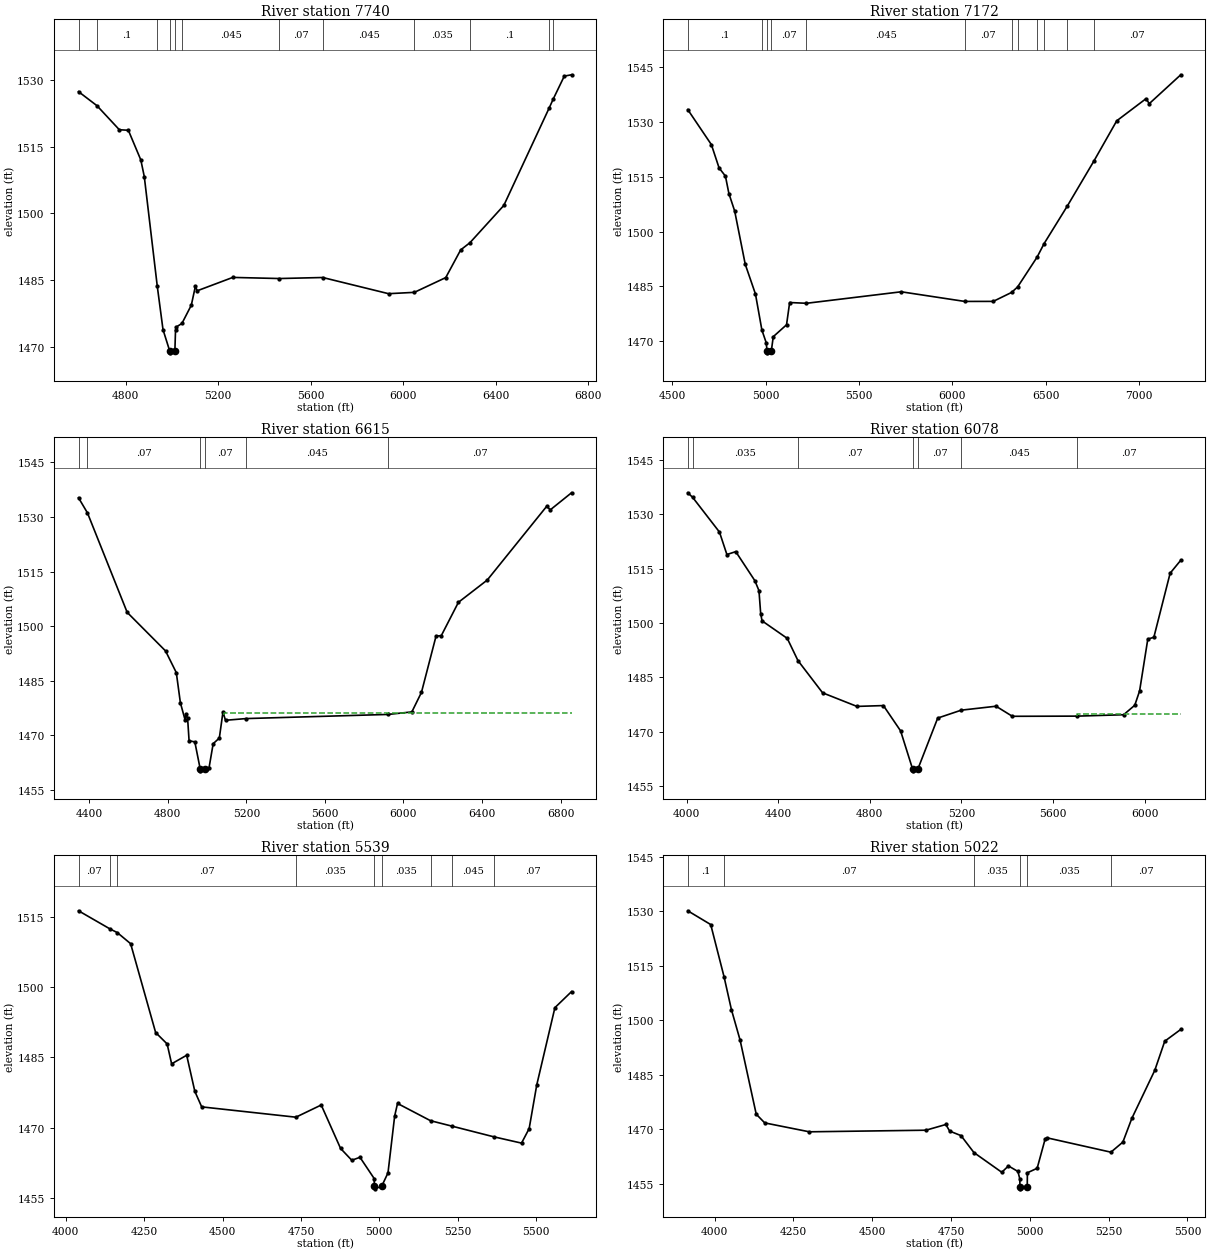
Type RM Length L Ch R = 1 ,7740    ,568,568,568
BEGIN DESCRIPTION:
North Creek 14.0
END DESCRIPTION:
XS GIS Cut Line= 3
      1995924.96       13910425.        1995525.       13910425.
      1994074.96     13911375.03
#Sta/Elev= 30
  4595.4 1527.32  4675.4 1524.16  4772.1 1518.77  4811.1 1518.65  4865.1 1511.99
  4880.1 1508.25  4936.2 1483.69  4961.1 1473.92  4989.6 1469.22  4990.1 1468.72
  5012.5 1469.22  5015.2 1473.74    5019 1474.54  5042.9 1475.31  5083.5  1479.4
  5101.5 1483.72  5108.6 1482.63  5262.9 1485.64  5464.7 1485.39  5652.2 1485.62
  5937.1 1481.99  6048.7 1482.29  6184.6  1485.6  6249.2 1491.81  6289.4 1493.43
  6435.8 1501.78    6632 1523.63  6650.3 1525.72  6697.6  1530.8  6728.9  1531.1
#Mann= 12 ,-1 , 0
  4595.4    .035       0  4675.4      .1       0  4936.2     .07       0
  4989.6     .05       0  5012.5     .07       0  5042.9    .045       0
  5464.7     .07       0  5652.2    .045       0  6048.7    .035       0
  6289.4      .1       0    6632     .07       0  6650.3      .1       0
Bank Sta=4989.6,5012.5
XS Rating Curve= 0 ,0
Exp/Cntr=0.3,0.1

Type RM Length L Ch R = 1 ,7172    ,557,557,557
BEGIN DESCRIPTION:
North Creek 13.0
END DESCRIPTION:
XS GIS Cut Line= 3
      1995725.05     13909824.99        1995325.       13909925.
      1993725.02     13911474.98
#Sta/Elev= 30
  4583.3  1533.4  4709.9  1523.8  4751.1 1517.42  4785.1 1515.18  4803.7  1510.4
  4834.6 1505.62  4891.3 1491.01  4945.9 1482.89  4980.3 1473.03  5003.7 1469.52
  5007.8 1467.28  5008.3 1466.78  5030.8 1467.28  5041.3 1471.21  5112.3 1474.46
    5129 1480.56  5219.2 1480.35  5726.3  1483.5  6066.6 1480.86  6219.1 1480.87
  6317.2 1483.32  6349.7 1484.83  6454.1    1493  6491.3 1496.68  6615.3 1506.94
  6758.1  1519.3  6880.4 1530.32  7037.4 1536.39  7054.6 1535.02  7223.3 1542.93
#Mann= 12 ,-1 , 0
  4583.3      .1       0  4980.3     .07       0  5007.8     .05       0
  5030.8     .07       0  5219.2    .045       0  6066.6     .07       0
  6317.2    .035       0  6349.7     .07       0  6454.1      .1       0
  6491.3     .07       0  6615.3      .1       0  6758.1     .07       0
Bank Sta=5007.8,5030.8
XS Rating Curve= 0 ,0
Exp/Cntr=0.3,0.1

Type RM Length L Ch R = 1 ,6615    ,537,537,537
BEGIN DESCRIPTION:
North Creek 12.0
END DESCRIPTION:
XS GIS Cut Line= 3
      1995575.04     13909274.98        1994975.       13909525.
      1993375.02     13910474.99
#Sta/Elev= 30
  4345.3 1535.28  4390.9 1531.12  4593.2 1503.79  4788.5  1493.2  4843.4 1487.23
  4864.2 1478.93  4888.9 1474.09  4892.2 1475.89  4900.9 1474.72  4908.4 1468.52
  4937.7  1468.2  4965.1 1460.75  4965.6 1460.25  4988.2 1460.75  5010.2 1461.11
  5031.1 1467.71  5062.5 1469.26  5080.9 1476.41  5093.9 1474.14  5198.6 1474.61
    5922 1475.75  6042.9 1476.44  6091.8  1481.8  6166.1 1497.26  6192.9  1497.4
    6280 1506.55  6426.7 1512.66  6730.2 1532.97  6747.7 1531.95  6856.1 1536.65
#Mann= 6 ,-1 , 0
  4345.3    .035       0  4390.9     .07       0  4965.1     .05       0
  4988.2     .07       0  5198.6    .045       0    5922     .07       0
#XS Ineff= 2 , 0
                         5084.92         1476.13
Permanent Ineff=
       F       F
Bank Sta=4965.1,4988.2
XS Rating Curve= 0 ,0
Exp/Cntr=0.3,0.1

Type RM Length L Ch R = 1 ,6078    ,539,539,539
BEGIN DESCRIPTION:
North Creek 11.0
END DESCRIPTION:
XS GIS Cut Line= 3
        1995325.       13908675.        1994525.       13909275.
      1993674.05       13910053.
#Sta/Elev= 30
  4005.2  1535.9  4026.2 1534.67  4143.7 1525.06  4176.2 1518.86  4214.9 1519.66
  4298.4 1511.63  4316.2  1508.9  4323.7 1502.57  4329.7 1500.56  4439.8 1495.72
  4486.4  1489.6  4594.1  1480.7  4744.1 1476.95  4859.7 1477.18  4934.7  1470.2
  4987.1 1459.67  4987.6 1459.17  5010.2 1459.67  5096.8 1473.73  5199.5 1475.91
  5351.5    1477  5422.7 1474.22  5706.6 1474.27  5908.6 1474.65  5957.4 1477.27
  5978.4 1481.21  6014.2 1495.51  6040.7 1496.03  6111.8 1513.71  6158.2 1517.28
#Mann= 7 ,-1 , 0
  4005.2     .07       0  4026.2    .035       0  4486.4     .07       0
  4987.1     .05       0  5010.2     .07       0  5199.5    .045       0
  5706.6     .07       0
#XS Ineff= 2 , 0
                         5705.79         1474.73
Permanent Ineff=
       F       F
Bank Sta=4987.1,5010.2
XS Rating Curve= 0 ,0
Exp/Cntr=0.3,0.1

Type RM Length L Ch R = 1 ,5539    ,517,517,517
BEGIN DESCRIPTION:
North Creek 10.0
END DESCRIPTION:
XS GIS Cut Line= 3
      1995064.66     13908554.56        1994175.       13908925.
      1993574.98       13909025.
#Sta/Elev= 30
  4040.8 1516.25    4142 1512.35  4164.4  1511.6    4207 1509.23  4286.7 1490.29
  4323.4 1487.85  4337.7 1483.61  4385.7 1485.44  4411.7 1477.74  4433.6 1474.43
  4733.9 1472.23  4814.7 1474.83  4876.4 1465.57  4912.2 1463.04  4938.2 1463.68
  4983.7 1459.13  4984.1 1457.45  4984.6 1456.95  5007.2 1457.45  5027.6 1460.36
  5048.9 1472.49    5058 1475.16  5163.2 1471.48  5231.6 1470.32  5364.1 1468.06
  5453.4  1466.7  5477.7  1469.8    5502 1479.14  5559.8 1495.59  5612.8 1499.01
#Mann= 9 ,-1 , 0
  4040.8     .07       0    4142      .1       0  4164.4     .07       0
  4733.9    .035       0  4984.1    .035       0  5007.2    .035       0
  5163.2     .07       0  5231.6    .045       0  5364.1     .07       0
Bank Sta=4984.1,5007.2
XS Rating Curve= 0 ,0
Exp/Cntr=0.3,0.1

Type RM Length L Ch R = 1 ,5022    ,533,533,533
BEGIN DESCRIPTION:
North Creek 9.0
END DESCRIPTION:
XS GIS Cut Line= 3
      1995061.93     13908395.05        1993975.       13908475.
      1993525.01       13908625.
#Sta/Elev= 30
  3914.5 1530.13  3987.4 1526.34  4029.7 1511.99    4053 1502.98  4080.6 1494.57
  4131.8  1474.2  4158.8 1471.81  4300.2 1469.36  4670.2  1469.8  4733.4 1471.37
  4745.4 1469.56  4781.5 1468.31  4822.5 1463.65  4910.9 1458.23  4931.9 1459.98
    4962 1458.46    4968 1456.43  4968.5 1454.18    4969 1453.68  4991.6 1454.18
  4992.1 1458.09  5023.1 1459.34  5048.4 1467.38  5054.7  1467.7  5257.1 1463.76
    5295 1466.53  5323.5 1473.06  5396.2 1486.25  5427.9 1494.27  5478.7 1497.51
#Mann= 6 ,-1 , 0
  3914.5      .1       0  4029.7     .07       0  4822.5    .035       0
  4968.5    .035       0  4991.6    .035       0  5257.1     .07       0
Bank Sta=4968.5,4991.6
XS Rating Curve= 0 ,0
Exp/Cntr=0.3,0.1

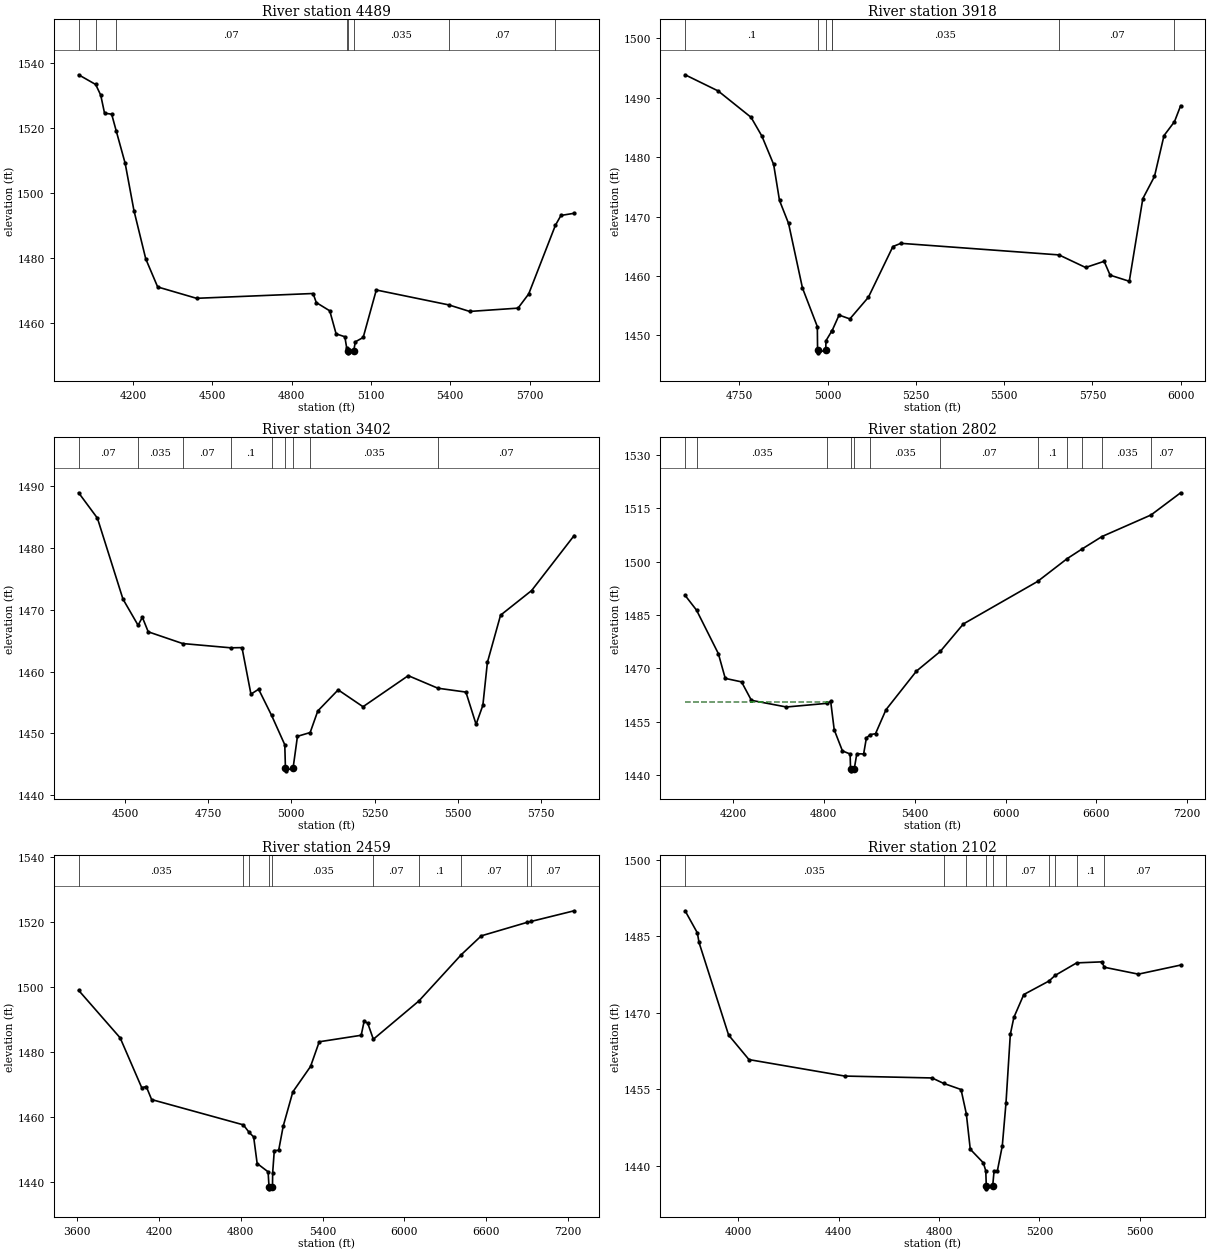
Type RM Length L Ch R = 1 ,4489    ,571,571,571
BEGIN DESCRIPTION:
North Creek 8.0
END DESCRIPTION:
XS GIS Cut Line= 3
      1995081.27     13907968.63        1994075.       13907975.
      1993352.11     13908456.39
#Sta/Elev= 30
  3994.1 1536.52  4058.6 1533.53  4077.7 1530.24  4092.1 1524.69  4119.1 1524.37
    4136 1519.31  4170.1 1509.24  4203.4 1494.66  4248.1 1479.76  4293.1 1471.12
  4440.1 1467.62  4881.2  1469.1  4893.2 1466.31  4944.2 1463.76  4968.2 1456.66
  5001.3 1455.77  5008.3 1452.29  5011.4 1451.31  5011.9 1450.81  5034.5 1451.31
    5041  1454.2  5070.7 1455.56  5120.3 1470.18  5394.9 1465.58  5473.5 1463.57
  5656.5 1464.59  5696.9 1468.97    5798 1490.15  5818.9 1493.16  5868.9 1493.83
#Mann= 8 ,-1 , 0
  3994.1     .07       0  4058.6      .1       0    4136     .07       0
  5008.3    .035       0  5011.4     .05       0  5034.5    .035       0
  5394.9     .07       0    5798    .035       0
Bank Sta=5011.4,5034.5
XS Rating Curve= 0 ,0
Exp/Cntr=0.3,0.1

Type RM Length L Ch R = 1 ,3918    ,516,516,516
BEGIN DESCRIPTION:
North Creek 7.0
END DESCRIPTION:
XS GIS Cut Line= 3
      1994274.98       13907425.        1993875.       13907475.
      1993274.99     13908275.01
#Sta/Elev= 30
  4596.7 1493.88  4690.2 1491.16  4783.4 1486.72  4814.1 1483.56  4847.4 1478.79
    4864 1472.72  4889.7 1468.84    4929 1457.98  4971.1 1451.48  4971.8 1447.56
  4972.3 1447.06    4995 1447.56  4995.5 1449.09  5011.4 1450.67  5012.3 1450.71
  5032.7 1453.42  5063.2 1452.77  5115.7 1456.42  5185.1 1464.96  5207.7  1465.5
  5655.4 1463.55  5730.7 1461.43  5783.2 1462.47  5800.1 1460.14  5854.4 1459.11
  5892.7 1473.02  5925.7 1476.76  5952.7 1483.64  5982.4 1485.99  5999.8 1488.67
#Mann= 7 ,-1 , 0
  4596.7      .1       0  4971.8     .05       0    4995      .1       0
  5011.4     .07       0  5012.3    .035       0  5655.4     .07       0
  5982.4      .1       0
#XS Ineff= 2 , 0
                         5779.42         1462.28
Permanent Ineff=
       F       F
Bank Sta=4971.8,4995
XS Rating Curve= 0 ,0
Exp/Cntr=0.3,0.1

Type RM Length L Ch R = 1 ,3402    ,600,600,600
BEGIN DESCRIPTION:
North Creek 6.0
END DESCRIPTION:
XS GIS Cut Line= 3
      1993874.99     13906725.02        1993475.       13907225.
        1993075.     13907975.01
#Sta/Elev= 30
  4360.2 1488.96  4416.7 1484.85  4493.5 1471.75    4539 1467.51  4551.9  1468.8
  4569.5 1466.45    4673 1464.55  4817.5 1463.86  4851.5 1463.89  4878.4 1456.36
  4901.5 1457.15  4940.4 1452.93  4980.2 1448.16  4982.1 1444.44  4982.6 1443.94
  5005.3 1444.44  5018.3 1449.53  5056.5 1450.14  5079.5 1453.64  5140.7 1457.05
  5215.5 1454.32  5351.5 1459.35  5440.5 1457.32  5524.9 1456.69  5555.5 1451.47
  5575.9 1454.55  5589.5 1461.49  5629.1 1469.14  5722.5 1473.13  5850.5 1482.04
#Mann= 9 ,-1 , 0
  4360.2     .07       0    4539    .035       0    4673     .07       0
  4817.5      .1       0  4940.4     .07       0  4982.1     .05       0
  5005.3     .07       0  5056.5    .035       0  5440.5     .07       0
Bank Sta=4982.1,5005.3
XS Rating Curve= 0 ,0
Exp/Cntr=0.3,0.1

Type RM Length L Ch R = 1 ,2802    ,343,343,343
BEGIN DESCRIPTION:
North Creek 5.0
END DESCRIPTION:
XS GIS Cut Line= 5
      1993766.38     13906617.75      1993127.94     13906887.83
        1992875.       13907225.      1992828.39      13907913.7
      1992800.45     13909379.64
#Sta/Elev= 30
  3884.9 1490.53  3960.5 1486.37  4104.4 1474.16    4150  1467.2  4257.5 1466.22
  4322.6 1461.03  4553.9 1459.16  4824.5  1460.2  4845.9 1460.76  4869.2 1452.77
  4923.5 1446.82  4974.2 1445.95  4977.1 1441.72  4977.6 1441.22  5001.4 1441.72
  5018.3 1446.02  5063.5 1445.96  5081.5 1450.43  5106.5  1451.4  5141.8 1451.65
  5210.8 1458.38  5412.2 1469.25  5569.1 1474.76  5721.9  1482.5  6211.3 1494.43
  6407.9 1500.88  6506.2 1503.59  6636.8 1507.06  6960.9 1513.13  7156.1 1519.36
#Mann= 12 ,-1 , 0
  3884.9      .1       0  3960.5    .035       0  4824.5     .07       0
  4977.1     .05       0  5001.4     .07       0  5106.5    .035       0
  5569.1     .07       0  6211.3      .1       0  6407.9    .035       0
  6506.2     .07       0  6636.8    .035       0  6960.9     .07       0
#XS Ineff= 2 , 0
         4830.67  1460.6
Permanent Ineff=
       F       F
Bank Sta=4977.1,5001.4
XS Rating Curve= 0 ,0
Exp/Cntr=0.3,0.1

Type RM Length L Ch R = 1 ,2459    ,357,357,357
BEGIN DESCRIPTION:
North Creek 4.0
END DESCRIPTION:
XS GIS Cut Line= 5
      1993858.07     13906470.81      1992737.54     13906951.02
      1992450.52      13907153.4       1992015.8     13907424.43
      1991085.17     13908664.36
#Sta/Elev= 30
  3611.2 1499.05  3915.7 1484.43    4074 1469.09  4107.1 1469.47  4146.3 1465.46
  4818.5 1457.69  4861.8 1455.34  4894.3 1453.98    4920  1445.8  5000.3 1443.24
  5007.1 1438.51  5007.6 1438.01  5032.3 1438.51  5033.8    1443  5045.6 1449.78
  5077.8 1449.86  5110.9 1457.27  5181.5 1467.82  5311.4 1475.64  5375.1 1483.23
  5682.7 1485.23  5704.1 1489.51  5730.4 1488.97  5771.8 1484.01  6105.4 1495.77
  6416.9 1510.03  6563.1  1515.8  6897.5 1519.93    6927 1520.22  7244.1 1523.51
#Mann= 10 ,-1 , 0
  3611.2    .035       0  4818.5    .063       0  4861.8    .035       0
  5007.1    .035       0  5032.3    .035       0  5771.8     .07       0
  6105.4      .1       0  6416.9     .07       0  6897.5    .035       0
    6927     .07       0
Bank Sta=5007.1,5032.3
XS Rating Curve= 0 ,0
Exp/Cntr=0.3,0.1

Type RM Length L Ch R = 1 ,2102    ,430,430,430
BEGIN DESCRIPTION:
North Creek 3.1
END DESCRIPTION:
XS GIS Cut Line= 4
      1993425.41     13906312.73      1992573.93     13906716.19
      1992091.78     13906934.99      1991635.64     13907149.58
#Sta/Elev= 30
  3787.5 1490.02  3836.4 1485.68    3843 1483.81    3961 1465.64  4042.2 1460.83
    4424  1457.6  4772.2 1457.23  4817.9 1456.17  4887.7 1454.96  4908.8  1450.2
  4924.5 1443.25  4976.5 1440.59  4986.4    1439  4988.4 1435.98  4988.9 1435.48
  5013.8 1435.98  5019.3 1438.92  5032.5 1438.99  5052.2  1443.9    5067 1452.35
  5084.2 1465.78  5098.4 1469.11  5137.9 1473.59  5238.3 1476.24  5263.1 1477.35
  5348.7  1479.8  5448.8    1480  5459.3 1478.94  5594.7 1477.59  5763.3 1479.37
#Mann= 10 ,-1 , 0
  3787.5    .035       0  4817.9    .063       0  4908.8    .035       0
  4988.4    .035       0  5013.8    .035       0    5067     .07       0
  5238.3      .1       0  5263.1    .035       0  5348.7      .1       0
  5459.3     .07       0
Bank Sta=4988.4,5013.8
XS Rating Curve= 0 ,0
Exp/Cntr=0.3,0.1

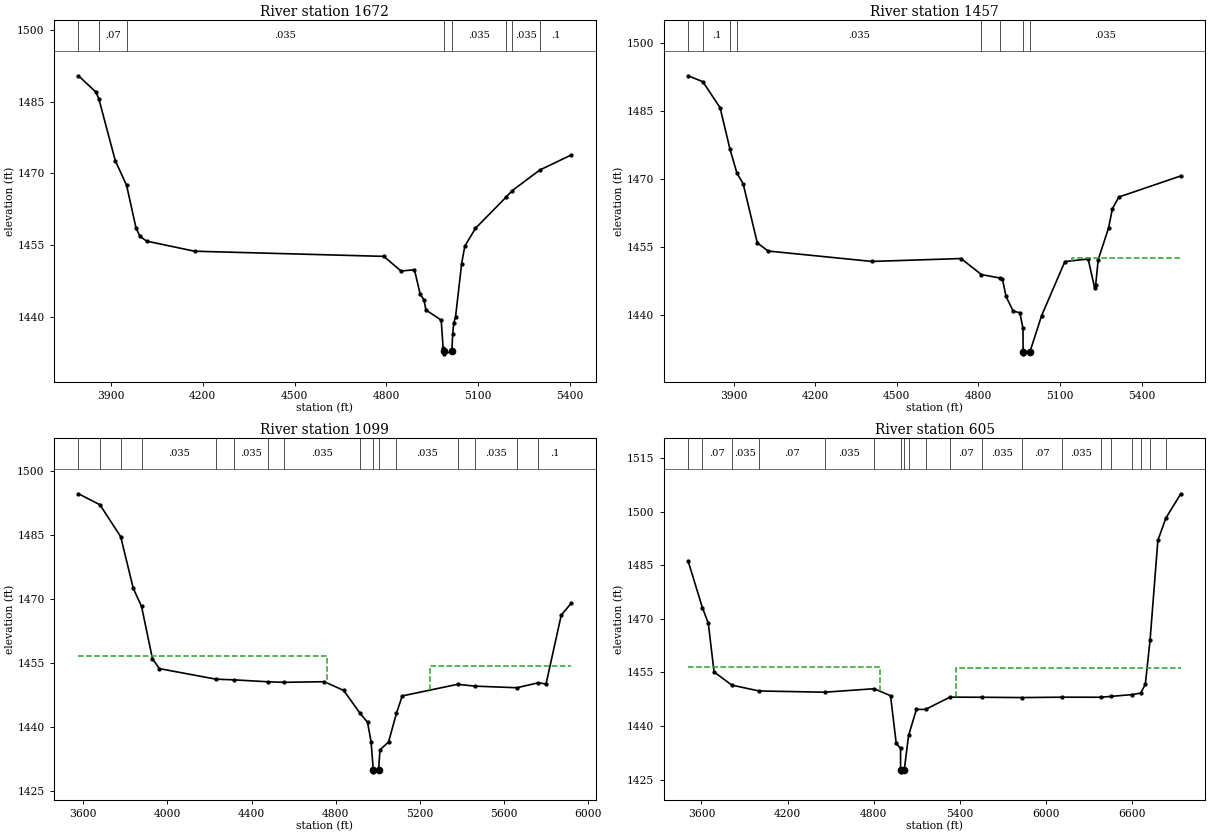
Type RM Length L Ch R = 1 ,1672    ,215,215,215
BEGIN DESCRIPTION:
North Creek 3.0
END DESCRIPTION:
XS GIS Cut Line= 3
      1993283.16     13906138.69        1992125.       13906475.
      1991925.01     13906824.99
#Sta/Elev= 30
    3794 1490.41  3851.1 1486.99  3860.5 1485.58  3914.2 1472.66  3951.1  1467.5
    3982 1458.57  3994.9 1456.81  4016.8 1455.82    4173 1453.71  4791.5 1452.63
  4847.7 1449.56  4891.5 1449.84  4910.2 1444.74  4922.7  1443.5  4928.9 1441.41
  4978.9  1439.3  4985.2 1433.44  4988.1 1432.74  4988.6 1432.24  5013.5 1432.74
  5016.5  1436.4  5019.7 1438.65  5025.7 1439.92  5045.7 1451.11    5056 1454.76
  5090.6 1458.48  5189.8 1464.95  5210.1 1466.34  5301.1  1470.7  5403.1 1473.82
#Mann= 8 ,-1 , 0
    3794    .035       0  3860.5     .07       0  3951.1    .035       0
  4988.1    .035       0  5013.5    .035       0  5189.8      .1       0
  5210.1    .035       0  5301.1      .1       0
#XS Ineff= 2 , 0
         4890.82 1449.81
Permanent Ineff=
       F       F
Bank Sta=4988.1,5013.5
XS Rating Curve= 0 ,0
Exp/Cntr=0.3,0.1

Type RM Length L Ch R = 1 ,1457    ,358,358,358
BEGIN DESCRIPTION:
Mapping XS 971778fe
END DESCRIPTION:
XS GIS Cut Line= 4
      1993275.34     13906056.72      1992140.69     13906225.64
      1991926.81     13906357.27       1991836.5     13906759.98
#Sta/Elev= 30
  3733.3 1492.77    3787 1491.46  3850.4 1485.74  3887.1 1476.51  3912.2 1471.35
  3935.6 1468.88  3987.2 1455.93  4026.6 1454.12  4408.8 1451.82  4736.3 1452.46
  4811.3 1448.92    4880 1448.16  4888.2 1448.02  4901.9 1444.09    4928 1440.87
  4952.6  1440.5  4964.1 1437.06  4964.6 1431.94  4965.1 1431.44    4990 1431.94
  5032.7 1439.89  5118.2 1451.79  5203.8 1452.36  5227.8 1445.91  5231.4 1446.66
  5240.7 1452.21  5278.9 1459.24  5292.9 1463.46  5316.6 1466.03  5544.3 1470.68
#Mann= 8 ,-1 , 0
  3733.3    .035       0    3787      .1       0  3887.1     .07       0
  3912.2    .035       0  4811.3     .07       0    4880    .035       0
  4964.6    .035       0    4990    .035       0
#XS Ineff= 2 , 0
                         5145.85         1452.63
Permanent Ineff=
       F       F
Bank Sta=4964.6,4990
XS Rating Curve= 0 ,0
Exp/Cntr=0.3,0.1

Type RM Length L Ch R = 1 ,1099    ,494,494,494
BEGIN DESCRIPTION:
North Creek 2.0
END DESCRIPTION:
XS GIS Cut Line= 4
      1993325.04       13906025.      1992083.67     13905890.35
      1991814.34     13906019.12      1991574.99     13906775.04
#Sta/Elev= 30
  3577.2 1494.69    3679 1492.12  3777.8 1484.61  3837.5 1472.48  3876.6 1468.28
  3928.5    1456  3961.2 1453.65  4230.8 1451.17  4316.8 1451.01  4476.9 1450.56
  4552.3 1450.43  4745.2 1450.58  4837.4 1448.52  4912.6 1443.32  4950.5 1441.04
  4967.1 1436.53  4977.7 1429.92  4978.2 1429.42  5003.1 1429.92  5009.4 1434.57
  5050.2 1436.43    5088 1443.18  5115.1 1447.24  5378.9 1449.97    5459 1449.54
  5659.8 1449.16  5761.9 1450.33  5798.4 1450.04  5870.8 1466.21  5917.3 1468.94
#Mann= 16 ,-1 , 0
  3577.2    .035       0    3679      .1       0  3777.8     .07       0
  3876.6    .035       0  4230.8     .07       0  4316.8    .035       0
  4476.9     .07       0  4552.3    .035       0  4912.6    .035       0
  4977.7    .035       0  5003.1    .035       0    5088    .035       0
  5378.9     .07       0    5459    .035       0  5659.8     .07       0
  5761.9      .1       0
#XS Ineff= 2 , 0
         4756.24 1456.57 5248.25         1454.17
Permanent Ineff=
       F       F
Bank Sta=4977.7,5003.1
XS Rating Curve= 0 ,0
Exp/Cntr=0.3,0.1

Type RM Length L Ch R = 1 ,605     ,0,0,0
BEGIN DESCRIPTION:
North Creek 1.0
END DESCRIPTION:
XS GIS Cut Line= 4
      1993124.97     13905874.99      1991912.35     13905451.77
       1991590.9     13905601.96      1990575.02     13907074.97
#Sta/Elev= 30
  3507.8 1486.06  3606.2 1473.14  3647.6 1468.76  3687.6 1455.12  3811.3 1451.43
  4000.8 1449.79  4459.5 1449.45  4800.8 1450.42  4915.9 1448.47  4955.6 1435.13
  4985.7 1433.72  4985.9 1427.66  4986.4 1427.16  5011.4 1427.66  5041.6 1437.34
  5096.1 1444.63  5159.9 1444.64  5329.6 1448.07  5551.6 1448.03  5832.9 1447.95
  6106.1 1448.05  6380.2 1448.04  6447.9 1448.27  6598.4 1448.78  6657.3 1449.21
  6689.4 1451.65  6722.3 1463.94  6776.8 1491.92  6832.4 1498.18  6936.3 1504.98
#Mann= 20 ,-1 , 0
  3507.8      .1       0  3606.2     .07       0  3811.3    .035       0
  4000.8     .07       0  4459.5    .035       0  4800.8    .035       0
  4985.9    .035       0  5011.4    .035       0  5041.6     .07       0
  5159.9    .035       0  5329.6     .07       0  5551.6    .035       0
  5832.9     .07       0  6106.1    .035       0  6380.2     .07       0
  6447.9    .035       0  6598.4     .07       0  6657.3    .035       0
  6722.3     .07       0  6832.4    .035       0
#XS Ineff= 2 , 0
         4846.15 1456.53 5374.13         1456.33
Permanent Ineff=
       F       F
Bank Sta=4985.9,5011.4
XS Rating Curve= 0 ,0
Exp/Cntr=0.3,0.1

Chan Stop Cuts=-1
Use User Specified Reach Order=0
Composite Channel Slope=5