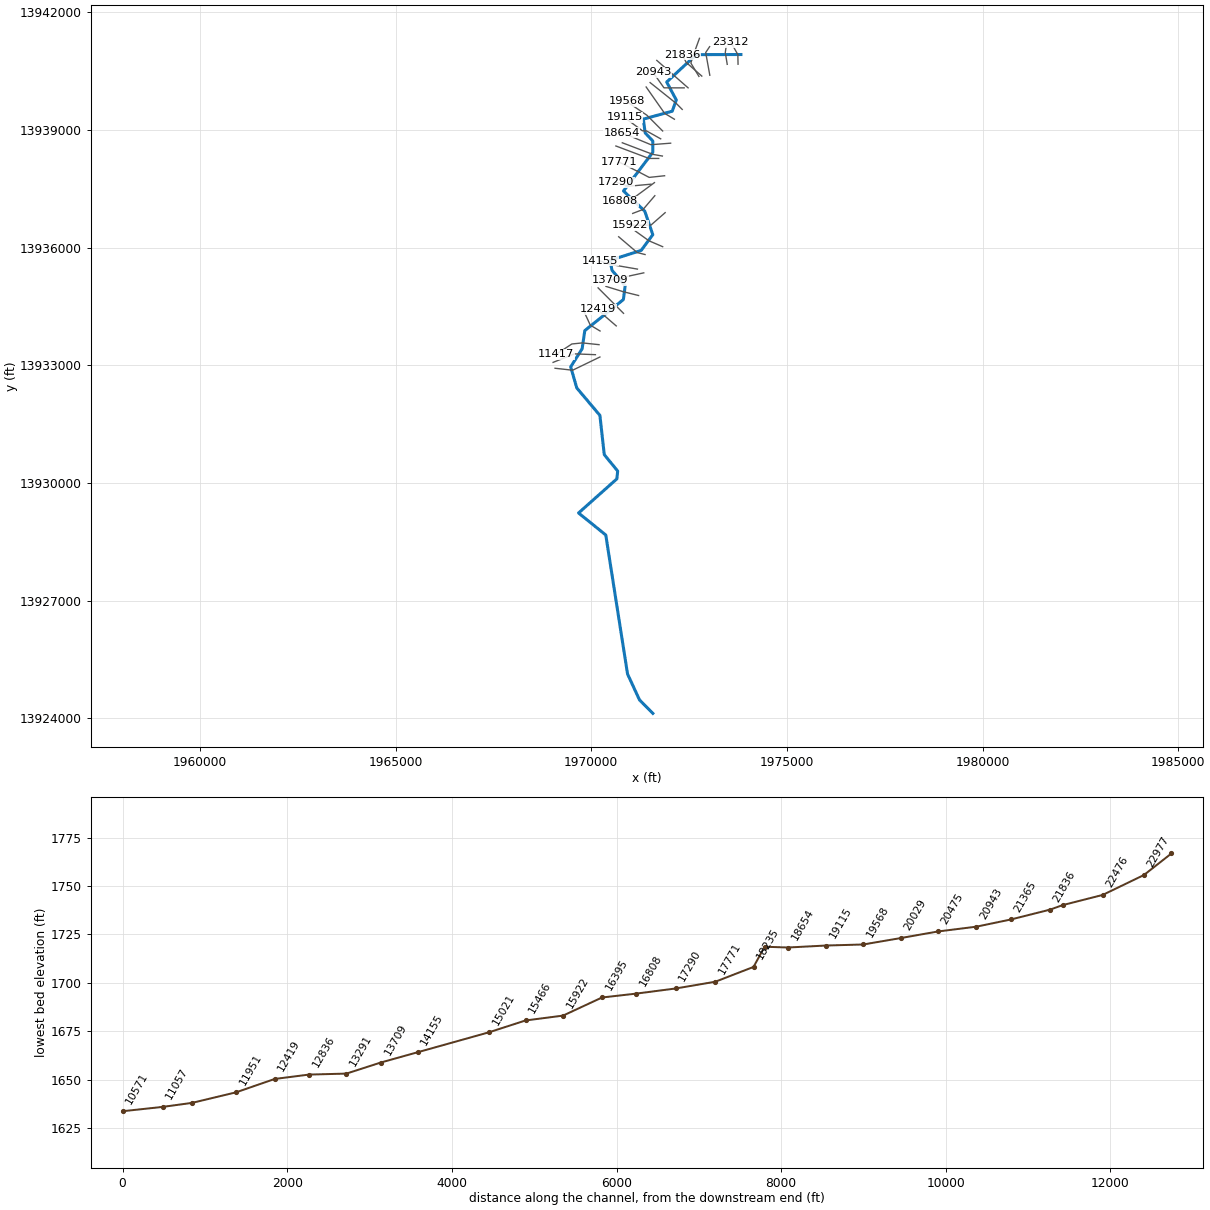
--- North Fork Cypress Creek.prj (project) ---

Proj Title=North Fork Cypress Creek Base Level Engineering
Current Plan=p01
Default Exp/Contr=0.3,0.1
English Units
Geom File=g01
Flow File=f01
Plan File=p01
Y Axis Title=Elevation
X Axis Title(PF)=Main Channel Distance
X Axis Title(XS)=Station
BEGIN DESCRIPTION:
North Fork Cypress Creek
END DESCRIPTION:
DSS Export Rating Curves= 0
DSS Export Rating Curve Sorted= 0
DSS Export Volume Flow Curves= 0
DXF OffsetX= 0
DXF OffsetY= 0
DXF ScaleX= 1
DXF ScaleY= 10

--- North Fork Cypress Creek.p01 (plan) ---

Plan Title=Multiple Run
Short Identifier=Multiple
Geom File=g01
Flow File=f01
Subcritical Flow
K Sum by GR= 0
Std Step Tol= 0.01
Critical Tol= 0.01
Num of Std Step Trials= 20
Max Error Tol= 0.3
Flow Tol Ratio= 0.001
Split Flow NTrial= 30
Split Flow Tol= 0.02
Split Flow Ratio= 0.02
Log Output Level= 0
Friction Slope Method= 1
Unsteady Friction Slope Method= 2
Unsteady Bridges Friction Slope Method= 1
Parabolic Critical Depth
Global Vel Dist=  1 , 1 , 1
Global Log Level= 0
CheckData=True
Encroach Param= -1, 0, 0, 0
BEGIN DESCRIPTION:
Multiple Run
END DESCRIPTION:

--- North Fork Cypress Creek.f01 (steady flow) ---

Flow Title=Multiple
Number of Profiles=7
Profile Names=10-year,25-year,50-year,1pct_min,100-year,1pct_plu,500-year
River Rch & RM= North Fork Cypre,Reach-1,23312
     971    1662    2328    1582    3156    6297    5755
River Rch & RM= North Fork Cypre,Reach-1,21836
    2211    3927    5631    3905    7791   15546   14815
River Rch & RM= North Fork Cypre,Reach-1,15466
    3032    5459    7900    5522   11019   21985   21294
River Rch & RM= North Fork Cypre,Reach-1,11417
    4366    7979   11662    8227   16416   32753   32307
River Rch & RM= North Fork Cypre,Reach-1,8722
    4369    7965   11623    8184   16329   32581   32017
River Rch & RM= North Fork Cypre,Reach-1,4056
    4372    7967   11623    8182   16325   32573   31991
River Rch & RM= North Fork Cypre,Reach-1,3112
    4481    8163   11905    8377   16715   33350   32727
Boundary for River Rch & Prof#=North Fork Cypre,Reach-1,1
Up Type=0
Dn Type=3
Dn Slope=0.005
Boundary for River Rch & Prof#=North Fork Cypre,Reach-1,2
Up Type=0
Dn Type=3
Dn Slope=0.005
Boundary for River Rch & Prof#=North Fork Cypre,Reach-1,3
Up Type=0
Dn Type=3
Dn Slope=0.005
Boundary for River Rch & Prof#=North Fork Cypre,Reach-1,4
Up Type=0
Dn Type=3
Dn Slope=0.005
Boundary for River Rch & Prof#=North Fork Cypre,Reach-1,5
Up Type=0
Dn Type=3
Dn Slope=0.005
Boundary for River Rch & Prof#=North Fork Cypre,Reach-1,6
Up Type=0
Dn Type=3
Dn Slope=0.005
Boundary for River Rch & Prof#=North Fork Cypre,Reach-1,7
Up Type=0
Dn Type=3
Dn Slope=0.005

--- North Fork Cypress Creek.g01 (geometry) ---

Geom Title=Existing Conditions
Program Version=4.10

River Reach=North Fork Cypre,Reach-1
Reach XY= 30
        1973825.       13940925.      1972682.72     13940921.81
      1971928.12     13940223.37      1972173.65     13939765.34
      1972069.56     13939480.19      1971330.45     13939277.47
      1971378.55     13938926.47       1971573.4     13938719.12
      1971573.16     13938431.13      1970824.88     13937445.09
      1971367.19     13936931.21      1971572.94     13936330.85
      1971277.31     13935930.82      1970480.45     13935677.47
      1970530.83      13935422.7      1970867.19     13935028.41
      1970821.25     13934676.55      1969835.48      13933884.8
      1969767.01     13933421.66      1969475.24      13932960.9
      1969630.54     13932422.58      1970221.46     13931723.54
      1970333.04     13930721.68      1970675.04     13930305.02
       1970655.4     13930104.84       1969675.7      13929234.8
      1970371.46     13928673.54      1970927.38     13925130.53
      1971232.86     13924468.83        1971575.       13924125.

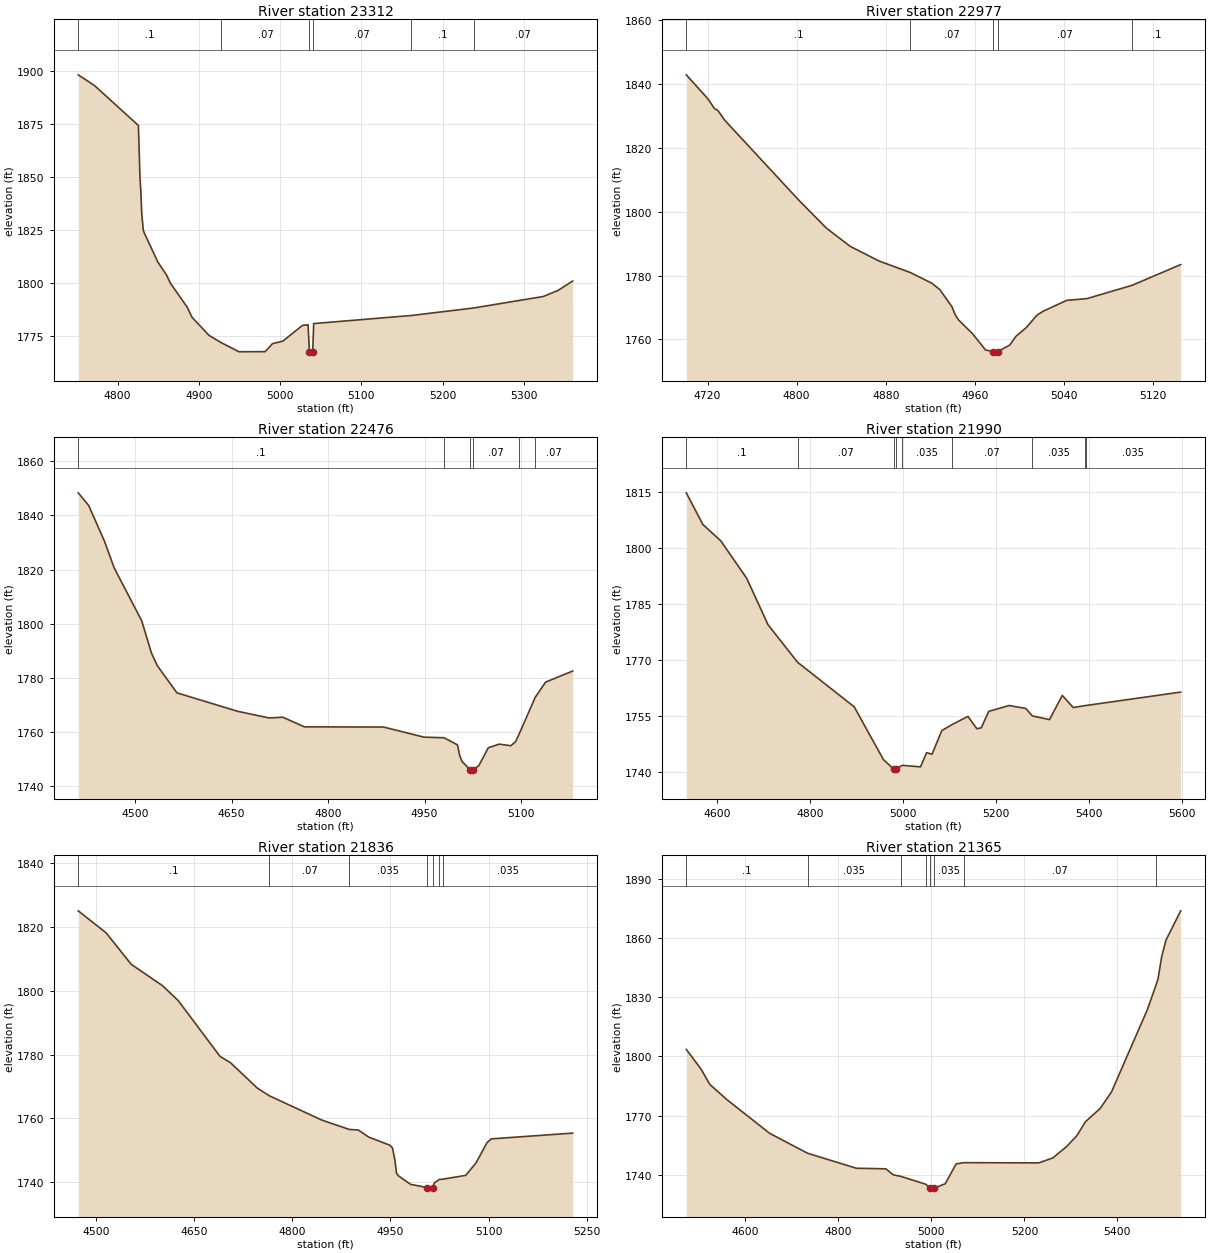
Type RM Length L Ch R = 1 ,23312   ,335,335,335
BEGIN DESCRIPTION:
North Fork Cypress Creek 3.0
END DESCRIPTION:
XS GIS Cut Line= 3
      1973751.69     13940677.05      1973746.19     13940922.98
      1973568.05     13941238.58
#Sta/Elev= 30
  4751.7 1898.29  4771.7 1893.23  4825.7 1874.38  4827.7 1849.32  4828.7 1843.62
  4829.8 1832.94  4831.7 1824.96  4832.8 1823.75  4849.7 1809.85  4860.5 1803.64
  4864.7 1800.11  4885.7  1788.6  4891.7 1783.79  4912.7 1775.23  4927.8 1771.79
  4949.5 1767.52  4981.7 1767.57  4990.7 1771.33  5003.5 1772.55  5027.6 1779.96
  5034.5 1780.26  5036.2 1767.37  5036.5 1766.87  5040.2 1767.37  5041.4 1780.82
  5161.6 1784.64  5238.2 1788.18  5323.8  1793.6  5341.9 1796.44  5360.1 1800.91
#Mann= 6 ,-1 , 0
  4751.7      .1       0  4927.8     .07       0  5036.2     .05       0
  5040.2     .07       0  5161.6      .1       0  5238.2     .07       0
Bank Sta=5036.2,5040.2
XS Rating Curve= 0 ,0
Exp/Cntr=0.3,0.1

Type RM Length L Ch R = 1 ,22977   ,501,501,501
BEGIN DESCRIPTION:
North Fork Cypress Creek 2.0
END DESCRIPTION:
XS GIS Cut Line= 3
        1973475.     13940674.98        1973425.       13940975.
      1973445.28     13941113.26
#Sta/Elev= 30
  4700.9 1842.89  4720.2 1835.42  4726.3 1832.28  4729.3 1831.71  4735.4 1828.67
  4802.3 1803.48  4826.7 1794.87    4848 1789.16  4873.9 1784.57    4902 1780.96
  4921.2 1777.64  4928.5 1775.63  4939.4 1770.24  4942.2 1767.84  4945.3 1766.11
  4957.7 1761.86  4969.6 1756.68  4976.7  1756.2    4977  1755.7  4980.5  1755.7
  4980.7  1756.2  4991.2  1758.2    4997    1761  5006.1 1763.68  5015.7 1767.57
  5021.3 1768.83  5042.5 1772.24  5060.6 1772.78    5101 1776.93  5144.8 1783.43
#Mann= 5 ,-1 , 0
  4700.9      .1       0    4902     .07       0  4976.7     .05       0
  4980.7     .07       0    5101      .1       0
Bank Sta=4976.7,4980.7
XS Rating Curve= 0 ,0
Exp/Cntr=0.3,0.1

Type RM Length L Ch R = 1 ,22476   ,486,486,486
BEGIN DESCRIPTION:
North Fork Cypress Creek 1.0
END DESCRIPTION:
XS GIS Cut Line= 3
      1973029.94     13940396.04        1972925.       13940975.
      1973025.02     13941125.03
#Sta/Elev= 30
  4411.5 1848.38  4427.7  1843.7  4452.1 1830.58  4467.4 1820.58  4510.1 1801.07
  4525.3 1789.09  4534.5  1784.4  4564.9 1774.37  4659.5 1767.53  4708.2 1765.09
  4729.6 1765.36  4763.1 1761.79  4886.3 1761.72  4949.1 1757.98  4980.1 1757.76
  5001.1 1755.13  5004.7 1751.06  5008.3 1748.95  5020.8 1745.91    5021 1745.41
  5024.8 1745.91  5034.2  1747.4    5049 1754.06    5066  1755.4  5084.1 1754.81
  5091.3 1756.27  5096.6 1758.93    5122 1772.71  5138.1 1778.34  5180.2 1782.44
#Mann= 6 ,-1 , 0
  4411.5      .1       0  4980.1     .07       0  5020.8     .05       0
  5024.8     .07       0  5096.6    .035       0    5122     .07       0
Bank Sta=5020.8,5024.8
XS Rating Curve= 0 ,0
Exp/Cntr=0.3,0.1

Type RM Length L Ch R = 1 ,21990   ,154,154,154
BEGIN DESCRIPTION:
North Fork Cypress Creek 0.0
END DESCRIPTION:
XS GIS Cut Line= 4
      1972751.71     13940366.57      1972547.25      13940703.7
      1972572.76     13940809.59      1972765.69     13941337.54
#Sta/Elev= 30
  4532.9 1814.85  4568.5 1806.37  4607.1 1801.98  4663.3 1791.86  4708.9 1779.47
  4772.7 1769.37  4894.8  1757.4  4957.4  1743.3    4980 1740.65  4980.3 1740.15
    4984 1740.65  4998.2  1741.7  5037.6  1741.3  5050.7 1745.11  5062.4 1744.69
  5083.4 1751.02  5104.7 1752.59  5139.8 1754.84    5159 1751.53  5168.6 1751.78
  5184.6 1756.19  5228.5 1757.76  5264.4 1756.98  5278.6 1754.96  5315.5 1753.98
  5343.1 1760.48  5366.6 1757.22  5391.7 1757.73  5393.1 1757.75  5598.2 1761.36
#Mann= 9 ,-1 , 0
  4532.9      .1       0  4772.7     .07       0    4980    .035       0
    4984     .07       0  4998.2    .035       0  5104.7     .07       0
  5278.6    .035       0  5391.7     .07       0  5393.1    .035       0
Bank Sta=4980,4984
XS Rating Curve= 0 ,0
Exp/Cntr=0.3,0.1

Type RM Length L Ch R = 1 ,21836   ,471,471,471
BEGIN DESCRIPTION:
North Fork Cypress Creek 44.0
END DESCRIPTION:
XS GIS Cut Line= 3
      1972824.98     13940375.02        1972425.       13940725.
      1972324.99     13940925.02
#Sta/Elev= 30
  4473.3 1825.12  4515.8 1818.22  4554.3 1808.32  4602.1 1801.62  4626.1 1796.93
  4689.8 1779.46  4705.8 1777.47  4746.8  1769.5  4765.1  1767.1  4845.3 1759.47
  4887.4 1756.53  4901.1 1756.35  4917.1 1754.12    4949  1751.6  4953.2 1750.75
  4956.9 1746.92  4959.4 1742.77  4962.3 1741.99  4980.8 1739.31    5006 1738.31
  5006.5 1737.81  5014.8 1738.31  5017.1 1739.76  5024.6 1740.84  5030.3 1740.94
  5065.1 1742.13  5080.8 1746.03  5097.6 1752.41  5104.3 1753.58  5228.4 1755.38
#Mann= 7 ,-1 , 0
  4473.3      .1       0  4765.1     .07       0  4887.4    .035       0
    5006    .035       0  5014.8    .035       0  5024.6     .07       0
  5030.3    .035       0
Bank Sta=5006,5014.8
XS Rating Curve= 0 ,0
Exp/Cntr=0.3,0.1

Type RM Length L Ch R = 1 ,21365   ,422,422,422
BEGIN DESCRIPTION:
North Fork Cypress Creek 43.0
END DESCRIPTION:
XS GIS Cut Line= 3
      1972475.04     13940074.97        1972075.       13940425.
      1971675.05     13940774.96
#Sta/Elev= 30
  4473.1 1803.53  4505.1 1793.43  4523.6  1785.8  4561.3 1777.92  4652.4 1761.01
  4733.9 1750.94  4838.5 1743.36  4902.3 1743.04  4918.3 1739.99  4934.5 1739.22
  4988.1 1735.24  4997.5 1733.27    4998 1732.77  5006.4 1733.27  5029.9 1735.51
  5053.3 1745.55  5069.7 1746.17    5231 1746.05  5261.1 1748.57  5290.2 1754.19
  5312.9 1759.82  5331.2 1766.87  5363.1 1773.64  5387.4 1782.02  5464.4 1823.63
    5482 1835.38  5487.3 1839.14  5495.2 1850.42  5504.3 1858.76  5536.1 1873.68
#Mann= 8 ,-1 , 0
  4473.1      .1       0  4733.9    .035       0  4934.5     .07       0
  4988.1    .035       0  4997.5    .035       0  5006.4    .035       0
  5069.7     .07       0    5482      .1       0
Bank Sta=4997.5,5006.4
XS Rating Curve= 0 ,0
Exp/Cntr=0.3,0.1

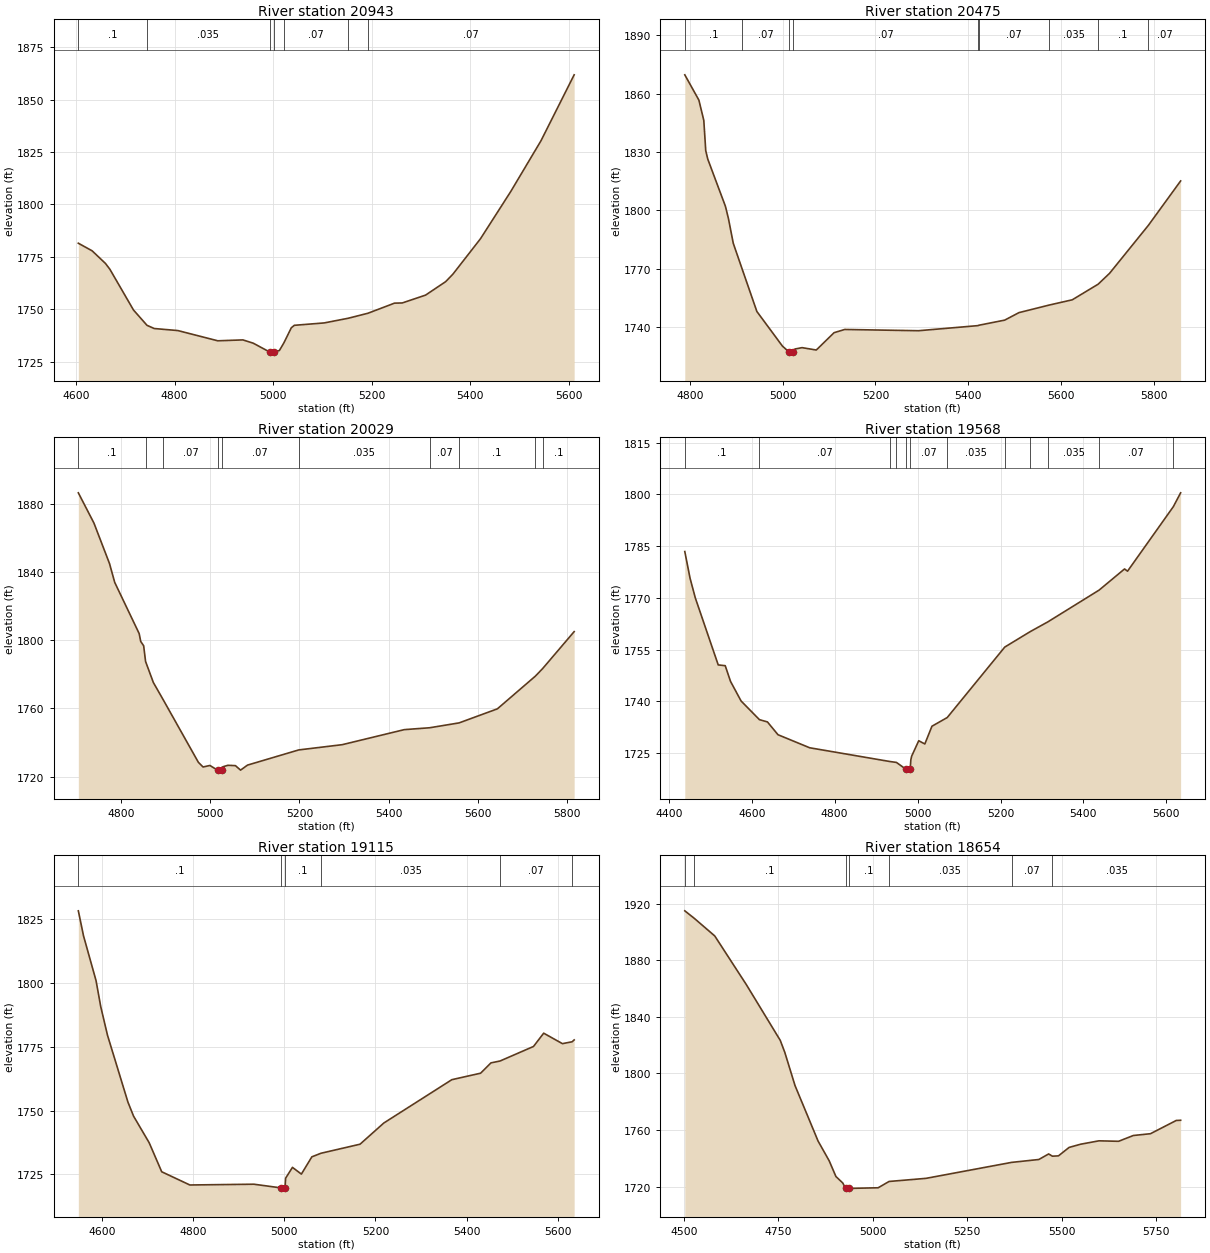
Type RM Length L Ch R = 1 ,20943   ,468,468,468
BEGIN DESCRIPTION:
North Fork Cypress Creek 42.0
END DESCRIPTION:
XS GIS Cut Line= 4
      1972375.04       13940075.        1971975.       13940075.
      1971858.43     13940075.78      1971575.01     13940474.99
#Sta/Elev= 30
  4604.7 1781.45  4632.7 1777.83  4659.7 1771.82  4668.7 1769.04  4716.7 1749.57
  4744.1 1742.28  4758.7 1740.76  4806.7 1739.78  4887.7  1734.9  4938.7 1735.33
  4959.7 1733.76  4993.2 1729.52  4993.7 1729.02  5002.2 1729.52  5012.8 1730.29
    5022 1733.98  5036.9 1741.11    5043 1742.29  5103.7 1743.43  5152.3 1745.65
  5192.5 1748.05  5246.4 1752.87    5262 1752.95  5309.3 1756.69  5350.1 1763.11
  5364.9 1766.71  5420.9 1783.62  5482.2 1806.11  5543.5  1830.3  5610.9 1861.79
#Mann= 7 ,-1 , 0
  4604.7      .1       0  4744.1    .035       0  4993.2    .035       0
  5002.2    .035       0    5022     .07       0  5152.3    .035       0
  5192.5     .07       0
Bank Sta=4993.2,5002.2
XS Rating Curve= 0 ,0
Exp/Cntr=0.3,0.1

Type RM Length L Ch R = 1 ,20475   ,446,446,446
BEGIN DESCRIPTION:
North Fork Cypress Creek 41.0
END DESCRIPTION:
XS GIS Cut Line= 3
        1972325.       13939525.        1972175.       13939675.
       1971504.1     13940209.32
#Sta/Elev= 30
  4788.6 1869.75    4819 1856.75  4829.6 1846.31  4833.8 1830.72  4838.1 1826.43
  4876.3 1802.07  4882.7 1795.86  4893.2 1783.04  4911.7 1770.27  4944.1 1747.96
  4999.3 1730.14  5013.9 1727.03  5014.4 1726.53  5022.9 1727.03  5026.3 1728.65
  5041.6 1729.35  5072.3 1728.13  5110.7 1737.05  5133.7 1738.71  5292.9 1738.06
  5421.5 1740.69  5422.9 1740.87  5478.8 1743.51  5509.6 1747.37  5574.7 1751.26
  5624.6 1753.97  5680.3 1761.98  5705.1  1767.6  5788.8 1792.28  5858.4 1815.13
#Mann= 9 ,-1 , 0
  4788.6      .1       0  4911.7     .07       0  5013.9     .05       0
  5022.9     .07       0  5421.5    .035       0  5422.9     .07       0
  5574.7    .035       0  5680.3      .1       0  5788.8     .07       0
Bank Sta=5013.9,5022.9
XS Rating Curve= 0 ,0
Exp/Cntr=0.3,0.1

Type RM Length L Ch R = 1 ,20029   ,461,461,461
BEGIN DESCRIPTION:
North Fork Cypress Creek 40.0
END DESCRIPTION:
XS GIS Cut Line= 3
      1972125.03     13939274.98        1971875.       13939425.
      1971403.17     13940097.01
#Sta/Elev= 30
  4703.7 1886.68  4738.7 1868.93  4773.7  1845.1  4785.4 1834.03  4840.2    1804
  4843.7 1799.37  4850.3 1796.81  4854.6  1787.6  4872.1 1775.22  4893.7 1765.33
  4973.1 1728.35  4983.6  1725.6    4999  1726.5  5016.5 1723.67    5017 1723.17
  5025.5 1723.67  5026.9 1725.62  5039.3  1726.6  5056.2  1726.4  5067.8 1723.76
  5083.3  1726.7  5198.2 1735.62  5295.9 1738.71  5435.2 1747.55  5492.1 1748.65
  5558.2 1751.51  5644.1 1759.76  5729.4 1778.99  5745.9 1783.49  5816.4 1805.13
#Mann= 10 ,-1 , 0
  4703.7      .1       0  4854.6     .07       0  4893.7     .07       0
  5016.5     .05       0  5025.5     .07       0  5198.2    .035       0
  5492.1     .07       0  5558.2      .1       0  5729.4     .07       0
  5745.9      .1       0
Bank Sta=5016.5,5025.5
XS Rating Curve= 0 ,0
Exp/Cntr=0.3,0.1

Type RM Length L Ch R = 1 ,19568   ,453,453,453
BEGIN DESCRIPTION:
North Fork Cypress Creek 39.0
END DESCRIPTION:
XS GIS Cut Line= 3
      1971824.97     13938975.03        1971425.       13939375.
      1970902.94     13939727.91
#Sta/Elev= 30
  4438.6 1783.46  4451.3 1775.72    4464 1770.01  4519.2  1750.6  4536.1 1750.37
  4548.9 1745.82  4574.3 1740.15  4618.6 1734.73  4637.9 1734.07  4663.4 1730.36
  4739.8 1726.58    4933  1722.6    4949 1722.33  4972.6 1720.31  4973.1 1719.81
  4982.1 1720.31  4983.8 1723.11  4985.8 1724.16  5002.8 1728.62  5017.5 1727.68
  5034.7 1732.83  5071.5 1735.34  5210.3 1755.77    5271  1760.2  5314.7 1763.11
  5437.8 1772.28  5499.1 1778.41  5506.4 1777.77  5616.9 1796.48  5634.4 1800.48
#Mann= 12 ,-1 , 0
  4438.6      .1       0  4618.6     .07       0    4933      .1       0
    4949     .07       0  4972.6     .05       0  4982.1     .07       0
  5071.5    .035       0  5210.3     .07       0    5271      .1       0
  5314.7    .035       0  5437.8     .07       0  5616.9      .1       0
Bank Sta=4972.6,4982.1
XS Rating Curve= 0 ,0
Exp/Cntr=0.3,0.1

Type RM Length L Ch R = 1 ,19115   ,461,461,461
BEGIN DESCRIPTION:
North Fork Cypress Creek 38.0
END DESCRIPTION:
XS GIS Cut Line= 4
      1971774.98     13938775.01      1971413.69     13938976.07
      1971307.03     13938980.76      1970850.25     13939319.32
#Sta/Elev= 30
  4547.5 1828.13  4558.9 1818.35  4586.4 1800.83  4596.7 1790.66  4611.5  1779.5
  4656.5 1753.27  4668.8 1747.82  4703.1 1737.41  4730.6 1726.06  4792.4 1720.89
  4933.1 1721.19  4991.9 1719.77  4992.4 1719.27  5001.4 1719.77  5002.7 1723.55
  5017.7 1727.78  5037.3 1725.15  5060.3  1731.9  5080.3  1733.3  5166.1 1736.84
  5218.4 1745.14  5367.7 1762.08  5430.9 1764.62  5453.6 1768.65  5473.6 1769.39
    5547 1775.07  5569.4 1780.27  5610.5 1776.18  5631.9 1776.91  5636.3 1777.63
#Mann= 6 ,-1 , 0
  4547.5      .1       0  4991.9     .05       0  5001.4      .1       0
  5080.3    .035       0  5473.6     .07       0  5631.9    .035       0
Bank Sta=4991.9,5001.4
XS Rating Curve= 0 ,0
Exp/Cntr=0.3,0.1

Type RM Length L Ch R = 1 ,18654   ,284,284,284
BEGIN DESCRIPTION:
North Fork Cypress Creek 37.0
END DESCRIPTION:
XS GIS Cut Line= 3
      1972029.02     13938664.28        1971525.       13938625.
      1970779.24     13938934.05
#Sta/Elev= 30
  4502.4 1915.01  4527.4 1909.73  4581.7 1897.26  4665.5 1862.77  4755.2  1823.4
  4767.2 1814.93  4794.3 1791.43  4855.3 1752.23  4884.6 1738.34  4902.6 1727.15
  4920.7 1722.59    4928 1718.75  4928.5 1718.25  4937.5 1718.75  5014.4 1719.21
  5043.2 1723.66  5141.1 1725.87  5367.7 1737.16  5439.8  1739.2  5465.8 1743.12
  5475.8 1741.54  5491.8 1741.78  5519.9 1747.73  5550.2 1749.99    5599  1752.4
  5650.9 1752.06  5689.9 1756.16  5735.4 1757.43  5803.5 1766.78  5815.2 1766.94
#Mann= 7 ,-1 , 0
  4502.4     .07       0  4527.4      .1       0    4928     .05       0
  4937.5      .1       0  5043.2    .035       0  5367.7     .07       0
  5475.8    .035       0
Bank Sta=4928,4937.5
XS Rating Curve= 0 ,0
Exp/Cntr=0.3,0.1

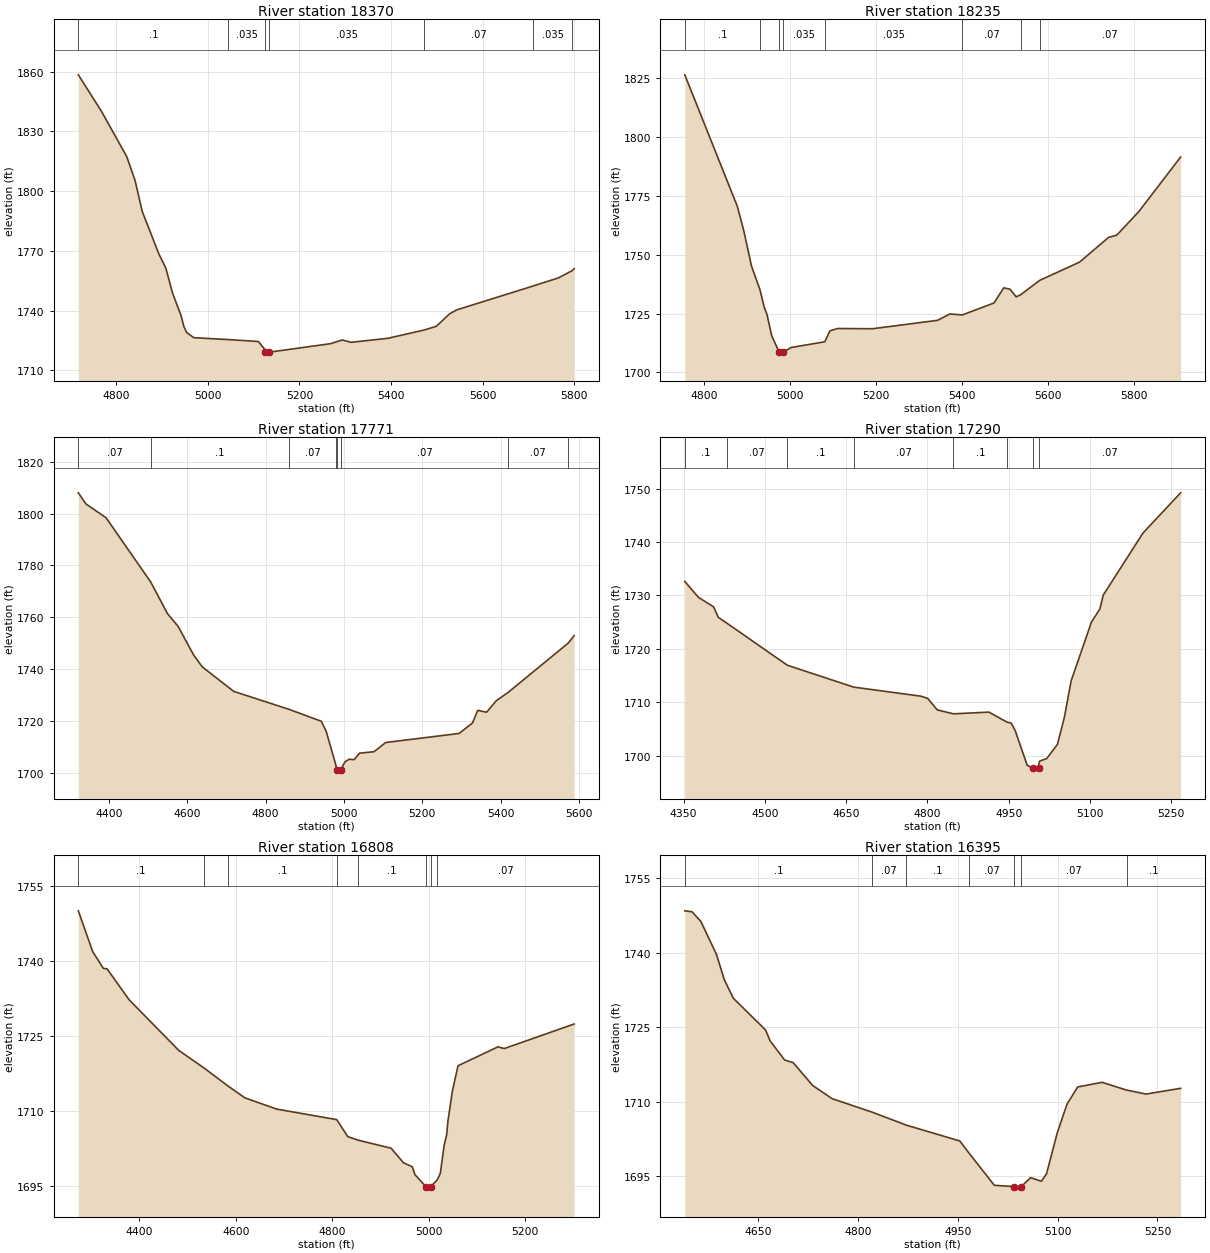
Type RM Length L Ch R = 1 ,18370   ,135,135,135
BEGIN DESCRIPTION:
North Fork Cypress Creek 37.1
END DESCRIPTION:
XS GIS Cut Line= 3
      1971818.09     13938336.12      1971570.68     13938379.53
      1970793.74     13938674.68
#Sta/Elev= 30
  4717.5 1858.45  4768.2 1840.05  4823.2 1817.36  4841.4 1805.36  4856.7 1790.03
  4893.2 1768.52  4908.4 1761.45  4923.3 1748.72    4942 1737.35    4948 1731.91
  4954.1 1728.99  4969.4 1726.41  5044.6 1725.46  5110.6 1724.49    5125 1720.39
  5125.1 1719.15  5125.6 1718.65  5134.7 1719.15  5267.9 1723.39  5293.5 1725.26
  5312.8 1724.08    5393 1726.09  5471.6 1730.21  5498.9 1732.11  5527.8 1738.38
  5543.8  1740.4  5710.7  1752.4  5765.3 1756.43  5795.7 1760.11  5799.8 1761.05
#Mann= 7 ,-1 , 0
  4717.5      .1       0  5044.6    .035       0  5125.1     .05       0
  5134.7    .035       0  5471.6     .07       0  5710.7    .035       0
  5795.7     .07       0
Bank Sta=5125.1,5134.7
XS Rating Curve= 0 ,0
Exp/Cntr=0.3,0.1

Type RM Length L Ch R = 1 ,18235   ,464,464,464
BEGIN DESCRIPTION:
North Fork Cypress Creek 36.0
END DESCRIPTION:
XS GIS Cut Line= 3
      1971725.01       13938275.        1971475.       13938275.
      1970630.03     13938592.61
#Sta/Elev= 30
    4755 1826.21    4877 1770.52    4892 1760.19    4910 1745.19  4929.4 1735.29
    4940 1727.49    4946 1724.67    4957 1715.59  4974.2 1708.71  4974.7 1708.21
  4983.8 1708.71    5003 1710.62  5080.4 1713.02  5092.6 1717.69  5110.3 1718.64
  5191.9 1718.56  5342.6 1722.12  5371.4 1724.82  5400.1  1724.4    5474 1729.48
  5496.4 1735.89    5511 1735.33  5525.3 1732.08  5535.8 1732.97  5580.3 1739.08
  5672.7 1746.79    5740 1757.25  5759.2 1758.23  5810.5 1768.21  5907.7 1791.36
#Mann= 8 ,-1 , 0
    4755      .1       0  4929.4    .035       0  4974.2     .05       0
  4983.8    .035       0  5080.4    .035       0  5400.1     .07       0
  5535.8    .035       0  5580.3     .07       0
Bank Sta=4974.2,4983.8
XS Rating Curve= 0 ,0
Exp/Cntr=0.3,0.1

Type RM Length L Ch R = 1 ,17771   ,481,481,481
BEGIN DESCRIPTION:
North Fork Cypress Creek 35.0
END DESCRIPTION:
XS GIS Cut Line= 4
      1971874.26     13937833.84      1971481.07     13937791.69
        1971225.       13937925.      1970704.82     13938184.61
#Sta/Elev= 30
  4321.9 1807.98  4341.3  1803.7  4392.6 1798.37  4506.6 1773.57  4549.4 1761.36
  4576.6 1756.42  4615.8 1745.49  4638.1 1740.81  4718.5 1731.34  4859.4 1724.42
  4941.8 1719.82  4954.1 1716.11  4978.9 1703.09  4981.7 1701.06  4982.2 1700.56
  4991.6 1701.06  5002.6 1704.18  5012.8 1705.13  5026.1 1705.01  5039.6  1707.5
  5076.4 1708.04  5106.6 1711.61  5293.8  1715.1  5327.9 1719.16  5341.3 1724.02
  5363.9  1723.3  5388.5  1727.7  5419.4 1731.01  5572.4 1749.99  5587.4 1752.85
#Mann= 8 ,-1 , 0
  4321.9     .07       0  4506.6      .1       0  4859.4     .07       0
  4978.9     .07       0  4981.7     .05       0  4991.6     .07       0
  5419.4     .07       0  5572.4      .1       0
Bank Sta=4981.7,4991.6
XS Rating Curve= 0 ,0
Exp/Cntr=0.3,0.1

Type RM Length L Ch R = 1 ,17290   ,482,482,482
BEGIN DESCRIPTION:
North Fork Cypress Creek 34.0
END DESCRIPTION:
XS GIS Cut Line= 4
      1971526.79     13937618.92      1970936.63      13937564.1
       1970845.4     13937605.28      1970631.85     13937666.68
#Sta/Elev= 30
  4352.3  1732.6  4377.6 1729.61  4405.3 1727.85  4414.3 1725.86  4430.3 1724.76
  4541.5 1716.91    4664 1712.81    4788 1711.11  4800.4 1710.71  4818.1 1708.55
  4848.1 1707.81  4913.5 1708.13    4947 1706.25  4954.6 1706.08  4961.9  1704.7
  4984.1 1698.19  4995.5 1697.58    4996 1697.08  5005.5 1697.58  5005.6 1698.39
  5007.1 1698.95  5020.3 1699.44    5040  1702.1  5052.8 1707.18  5065.3 1713.99
  5102.7 1724.97  5118.3 1727.45  5124.6 1730.05    5198 1741.68  5267.3 1749.19
#Mann= 8 ,-1 , 0
  4352.3      .1       0  4430.3     .07       0  4541.5      .1       0
    4664     .07       0  4848.1      .1       0    4947     .07       0
  4995.5     .05       0  5005.5     .07       0
Bank Sta=4995.5,5005.5
XS Rating Curve= 0 ,0
Exp/Cntr=0.3,0.1

Type RM Length L Ch R = 1 ,16808   ,413,413,413
BEGIN DESCRIPTION:
North Fork Cypress Creek 33.0
END DESCRIPTION:
XS GIS Cut Line= 3
      1971615.06     13937658.38        1971025.       13937225.
      1970733.04      13937178.2
#Sta/Elev= 30
  4273.5 1750.08  4303.3 1741.92  4325.3 1738.57  4333.1 1738.47  4378.9 1732.28
    4482 1722.13  4534.2 1718.64  4583.8 1715.03  4618.7 1712.67  4684.6 1710.42
  4809.2 1708.31  4831.9 1704.92  4853.4 1704.21  4921.9 1702.59  4947.3  1699.7
  4965.9 1698.87  4971.2 1697.31  4994.1 1694.91  4994.6 1694.41  5004.1 1694.91
  5017.7 1696.29  5023.9 1697.57  5031.8 1703.18    5037 1705.27  5039.6 1707.97
  5049.1 1714.15  5060.6 1719.09  5143.3 1722.87  5156.4 1722.53  5301.3 1727.44
#Mann= 8 ,-1 , 0
  4273.5      .1       0  4534.2     .07       0  4583.8      .1       0
  4809.2     .07       0  4853.4      .1       0  4994.1     .05       0
  5004.1      .1       0  5017.7     .07       0
Bank Sta=4994.1,5004.1
XS Rating Curve= 0 ,0
Exp/Cntr=0.3,0.1

Type RM Length L Ch R = 1 ,16395   ,473,473,473
BEGIN DESCRIPTION:
North Fork Cypress Creek 32.0
END DESCRIPTION:
XS GIS Cut Line= 3
      1971625.02     13937325.02        1971325.       13936975.
      1971059.59     13936872.85
#Sta/Elev= 30
  4539.5 1748.44  4550.3 1748.25  4563.6 1746.32  4587.1 1739.67  4598.8  1734.6
  4612.5 1730.84  4660.9 1724.46  4667.9 1722.24  4689.6 1718.41  4702.4 1717.88
  4731.7 1713.29  4760.8 1710.64  4820.6 1707.94  4872.6  1705.3    4953 1702.11
  4966.7 1699.69  5004.8 1693.19  5035.1 1692.92  5035.6 1692.42  5045.1 1692.92
  5059.4 1694.73  5075.5    1694  5083.3  1695.5  5099.5 1703.78  5114.1 1709.51
  5130.1 1712.98  5166.8 1713.92  5203.6 1712.36    5233 1711.56  5284.9 1712.71
#Mann= 7 ,-1 , 0
  4539.5      .1       0  4820.6     .07       0  4872.6      .1       0
  4966.7     .07       0  5035.1     .05       0  5045.1     .07       0
  5203.6      .1       0
Bank Sta=5035.1,5045.1
XS Rating Curve= 0 ,0
Exp/Cntr=0.3,0.1

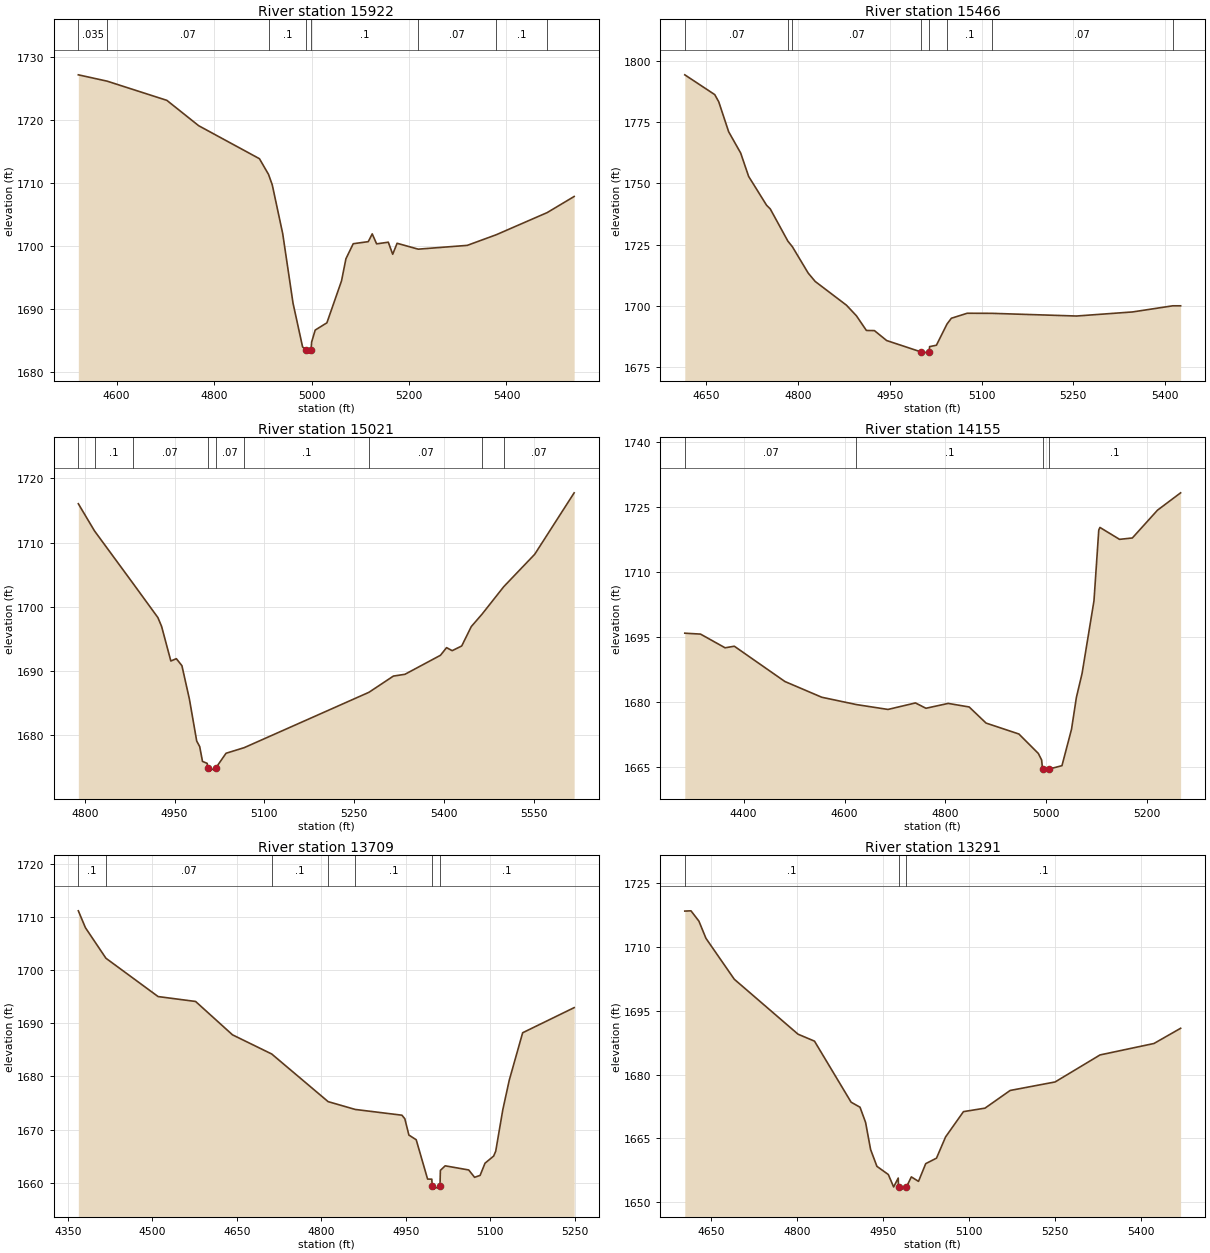
Type RM Length L Ch R = 1 ,15922   ,456,456,456
BEGIN DESCRIPTION:
North Fork Cypress Creek 31.0
END DESCRIPTION:
XS GIS Cut Line= 3
      1971889.12     13936892.35        1971525.       13936575.
      1970990.72      13936570.8
#Sta/Elev= 30
  4521.6 1727.12  4580.6 1726.12  4703.2 1723.08  4768.6 1719.06  4893.2 1713.84
  4911.8 1711.36  4919.5  1709.7  4940.9 1701.99  4962.1 1690.97  4981.7 1684.05
  4988.9 1683.56  4989.4 1683.06    4999 1683.56  5000.3 1684.82  5007.6 1686.71
  5031.6 1687.86  5061.6  1694.5  5070.6 1697.99  5085.6 1700.38  5116.5 1700.71
  5124.6 1701.94  5133.6 1700.36  5157.6 1700.62  5166.6 1698.71  5175.6 1700.45
  5218.9 1699.52  5319.6 1700.12    5379  1701.8  5483.6 1705.31  5538.9 1707.86
#Mann= 8 ,-1 , 0
  4521.6    .035       0  4580.6     .07       0  4911.8      .1       0
  4988.9     .05       0    4999      .1       0  5218.9     .07       0
    5379      .1       0  5483.6     .07       0
Bank Sta=4988.9,4999
XS Rating Curve= 0 ,0
Exp/Cntr=0.3,0.1

Type RM Length L Ch R = 1 ,15466   ,445,445,445
BEGIN DESCRIPTION:
North Fork Cypress Creek 30.0
END DESCRIPTION:
XS GIS Cut Line= 3
      1971825.01       13936025.        1971475.       13936175.
      1971125.01     13936424.99
#Sta/Elev= 30
  4614.7 1794.47  4663.7 1786.37  4670.2 1783.44  4686.5 1771.14  4706.1 1762.46
  4719.1 1752.89  4748.5 1741.06  4754.4 1739.61  4783.3 1726.39  4790.8 1724.05
  4816.5 1713.32    4828 1709.88  4879.1 1700.17  4895.4 1695.83  4911.7 1689.83
  4924.8 1689.77  4944.8 1685.71    5001 1681.05  5001.5 1680.55  5014.3 1681.05
  5015.1 1683.22  5026.2 1683.78  5043.6 1692.49  5050.7 1694.83  5076.5 1696.87
  5116.6 1696.84  5255.3 1695.74    5347 1697.41  5412.8 1699.92  5425.6 1699.92
#Mann= 8 ,-1 , 0
  4614.7     .07       0  4783.3    .035       0  4790.8     .07       0
    5001     .05       0  5014.3     .07       0  5043.6      .1       0
  5116.6     .07       0  5412.8      .1       0
Bank Sta=5001,5014.3
XS Rating Curve= 0 ,0
Exp/Cntr=0.3,0.1

Type RM Length L Ch R = 1 ,15021   ,866,866,866
BEGIN DESCRIPTION:
North Fork Cypress Creek 29.0
END DESCRIPTION:
XS GIS Cut Line= 3
      1971374.96     13935825.01        1971175.       13935875.
      1970700.82     13936278.15
#Sta/Elev= 30
  4789.2 1716.06  4816.3 1711.82    4880 1703.73  4922.1 1698.34  4928.3 1696.97
  4943.8 1691.57    4953 1691.93  4962.3 1690.84  4974.8 1685.64    4987 1679.11
    4992 1678.24  4996.7 1675.93  5004.5 1675.63  5005.7 1674.92  5006.2 1674.42
    5019 1674.92    5036  1677.2  5066.5 1678.08  5274.9  1686.7  5315.6 1689.22
    5335  1689.5  5394.3 1692.46  5404.5 1693.65  5413.9 1693.18  5429.8 1693.91
  5445.8 1696.93    5464 1698.89  5500.1 1703.15  5551.8 1708.19  5617.7 1717.76
#Mann= 9 ,-1 , 0
  4789.2     .07       0  4816.3      .1       0    4880     .07       0
  5005.7     .05       0    5019     .07       0  5066.5      .1       0
  5274.9     .07       0    5464      .1       0  5500.1     .07       0
Bank Sta=5005.7,5019
XS Rating Curve= 0 ,0
Exp/Cntr=0.3,0.1

Type RM Length L Ch R = 1 ,14155   ,446,446,446
BEGIN DESCRIPTION:
North Fork Cypress Creek 28.0
END DESCRIPTION:
XS GIS Cut Line= 3
      1971180.77     13935453.31        1970475.       13935575.
      1970222.57     13935662.05
#Sta/Elev= 30
  4283.3 1695.96  4314.5 1695.75  4363.2 1692.59  4381.5 1692.95  4481.9  1684.8
    4555 1681.17  4623.7 1679.48  4686.2 1678.36  4740.7 1679.86  4761.5 1678.63
  4805.6 1679.75  4847.2 1678.93  4880.7 1675.21  4945.8 1672.69  4984.3 1668.21
  4990.9 1666.69  4992.7 1664.62  4993.2 1664.12  5006.3 1664.62  5031.2 1665.38
  5050.2 1673.81  5059.8 1681.13  5071.1 1686.68  5094.7 1703.45  5104.2 1719.76
  5106.5 1720.37  5145.4 1717.62  5170.8 1717.94  5220.6 1724.35  5266.5 1728.36
#Mann= 4 ,-1 , 0
  4283.3     .07       0  4623.7      .1       0  4992.7     .05       0
  5006.3      .1       0
Bank Sta=4992.7,5006.3
XS Rating Curve= 0 ,0
Exp/Cntr=0.3,0.1

Type RM Length L Ch R = 1 ,13709   ,418,418,418
BEGIN DESCRIPTION:
North Fork Cypress Creek 27.0
END DESCRIPTION:
XS GIS Cut Line= 3
      1971342.45     13935357.85        1970725.       13935225.
      1970482.47     13935171.71
#Sta/Elev= 30
  4368.7 1711.12  4381.4 1707.93  4417.7 1702.21  4510.3 1695.01  4576.8 1694.09
  4642.3 1687.82  4711.9 1684.22    4812 1675.27  4860.1  1673.8    4943 1672.72
  4948.1 1672.05  4955.3 1668.99  4968.3 1668.11  4988.5 1660.72    4996  1660.7
  4996.7 1659.33  4997.2 1658.83  5010.5 1659.33  5011.2 1662.35  5019.7 1663.21
  5061.5 1662.43  5071.9 1661.05  5081.7 1661.41  5090.4  1663.7  5105.7 1665.04
  5109.4 1665.95    5122 1673.76  5133.4 1679.29  5157.2 1688.21  5248.6 1692.93
#Mann= 7 ,-1 , 0
  4368.7      .1       0  4417.7     .07       0  4711.9      .1       0
    4812     .07       0  4860.1      .1       0  4996.7     .05       0
  5010.5      .1       0
Bank Sta=4996.7,5010.5
XS Rating Curve= 0 ,0
Exp/Cntr=0.3,0.1

Type RM Length L Ch R = 1 ,13291   ,455,455,455
BEGIN DESCRIPTION:
North Fork Cypress Creek 26.0
END DESCRIPTION:
XS GIS Cut Line= 3
      1971209.92     13934779.82        1970825.       13934875.
      1970376.53     13935012.55
#Sta/Elev= 30
  4603.4 1718.37  4614.2 1718.43    4628 1716.02  4640.4 1711.96  4689.8 1702.37
  4801.1 1689.47  4829.8 1687.84  4893.8  1673.5  4909.3 1672.33    4919 1668.77
  4927.8 1662.38  4938.8 1658.45  4958.7 1656.53    4968 1653.61    4976  1655.7
  4976.5  1653.6    4977  1653.1  4990.3  1653.6  4998.9 1655.97  5011.4 1654.92
    5024 1659.08  5042.8 1660.37  5058.7 1665.36  5089.9 1671.29  5127.5 1672.11
  5171.4 1676.26  5249.9 1678.26  5328.3  1684.6  5422.5 1687.29    5469 1690.86
#Mann= 3 ,-1 , 0
  4603.4      .1       0  4976.5     .05       0  4990.3      .1       0
Bank Sta=4976.5,4990.3
XS Rating Curve= 0 ,0
Exp/Cntr=0.3,0.1

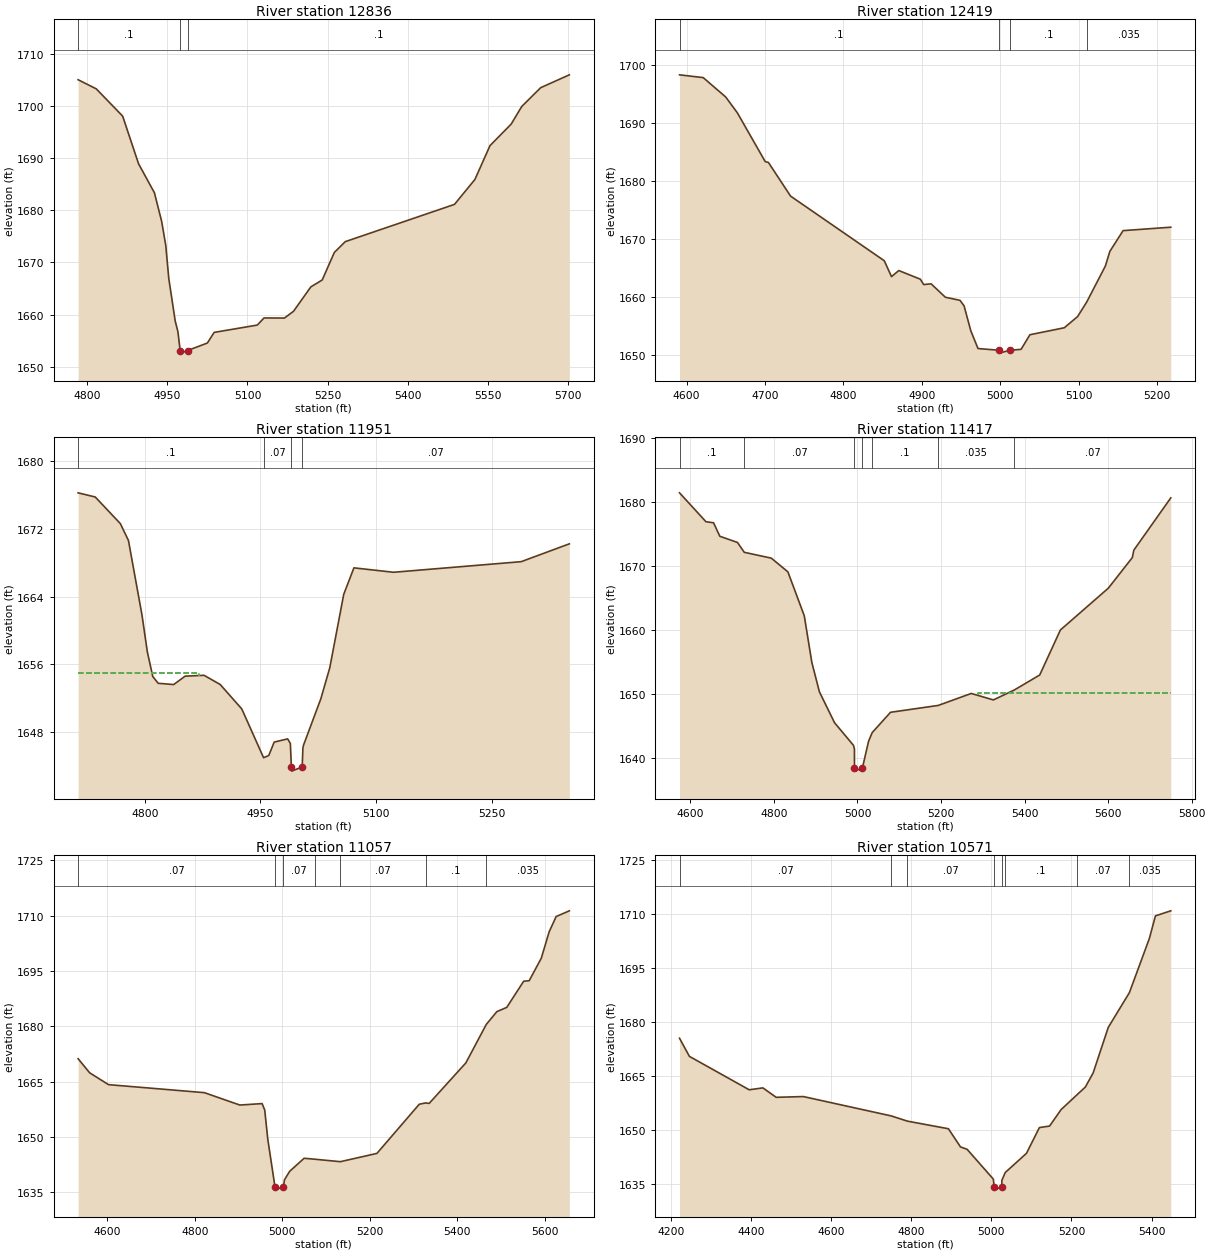
Type RM Length L Ch R = 1 ,12836   ,417,417,417
BEGIN DESCRIPTION:
North Fork Cypress Creek 25.0
END DESCRIPTION:
XS GIS Cut Line= 3
      1970824.98     13934325.02        1970675.       13934475.
      1970175.01     13934974.99
#Sta/Elev= 30
  4783.1 1705.05  4817.1  1703.3  4866.5 1698.06  4896.2 1688.93  4925.9 1683.36
  4939.4 1677.89  4947.1  1673.3  4952.8 1666.91  4964.8 1658.76  4969.8 1656.73
  4974.1 1653.09  4974.6 1652.59    4988 1653.09    5025 1654.53  5037.7 1656.57
  5118.3 1657.97    5131 1659.34  5169.2 1659.32  5186.2 1660.62  5218.6  1665.3
  5239.9 1666.63  5262.5  1671.9    5283 1673.98  5487.4 1681.13  5525.6 1685.91
  5553.8  1692.4  5593.5 1696.54  5613.2 1699.91  5648.6 1703.52  5702.3 1705.99
#Mann= 3 ,-1 , 0
  4783.1      .1       0  4974.1     .05       0    4988      .1       0
Bank Sta=4974.1,4988
XS Rating Curve= 0 ,0
Exp/Cntr=0.3,0.1

Type RM Length L Ch R = 1 ,12419   ,468,468,468
BEGIN DESCRIPTION:
North Fork Cypress Creek 24.0
END DESCRIPTION:
XS GIS Cut Line= 3
      1970638.85     13934004.62        1970325.       13934275.
      1970174.99     13934425.01
#Sta/Elev= 30
    4591 1698.28  4621.2  1697.8  4649.9 1694.46  4664.7 1691.74  4700.3 1683.32
  4704.3 1683.19  4732.6 1677.38  4852.1 1666.24  4861.3  1663.5  4870.6 1664.55
  4898.1 1663.06  4902.3 1662.14  4911.8 1662.26    4930 1659.95  4948.6 1659.42
  4953.8 1658.48  4962.4 1654.18  4971.6 1651.11  4998.3 1650.82  4998.8 1650.32
  5012.2 1650.82  5026.5 1650.97  5037.8 1653.49  5081.6 1654.69  5098.6 1656.62
  5110.2 1659.12    5134 1665.33  5139.7 1667.85  5156.6 1671.43  5217.4 1672.02
#Mann= 4 ,-1 , 0
    4591      .1       0  4998.3     .05       0  5012.2      .1       0
  5110.2    .035       0
Bank Sta=4998.3,5012.2
XS Rating Curve= 0 ,0
Exp/Cntr=0.3,0.1

Type RM Length L Ch R = 1 ,11951   ,534,534,534
BEGIN DESCRIPTION:
North Fork Cypress Creek 23.0
END DESCRIPTION:
XS GIS Cut Line= 3
        1970225.       13933875.        1969975.       13934025.
      1969830.98     13934338.89
#Sta/Elev= 30
  4713.6 1676.22  4735.8 1675.73  4768.4 1672.59  4778.9  1670.6  4796.4 1661.84
  4803.4 1657.47  4810.4 1654.58  4817.4 1653.78  4837.5 1653.63  4852.4 1654.62
  4876.9 1654.72  4897.8 1653.64  4925.8 1650.76  4954.1 1645.01  4960.8 1645.27
  4967.8 1646.85  4985.3 1647.23  4988.8 1646.69  4990.1 1643.93  4990.6 1643.43
  5004.1 1643.93  5005.1 1646.17  5005.9  1646.5  5028.3 1651.95  5039.9 1655.61
    5058 1664.26  5071.2 1667.38  5122.6 1666.86  5288.1 1668.11  5350.5 1670.21
#Mann= 4 ,-1 , 0
  4713.6      .1       0  4954.1     .07       0  4990.1     .05       0
  5004.1     .07       0
#XS Ineff= 2 , 0
         4870.29 1655.01
Permanent Ineff=
       F       F
Bank Sta=4990.1,5004.1
XS Rating Curve= 0 ,0
Exp/Cntr=0.3,0.1

Type RM Length L Ch R = 1 ,11417   ,360,360,360
BEGIN DESCRIPTION:
North Fork Cypress Creek 22.0
END DESCRIPTION:
XS GIS Cut Line= 4
        1970199.     13933526.58       1969774.8     13933571.38
      1969504.43     13933544.09      1969105.12     13933282.08
#Sta/Elev= 30
  4574.1  1681.4  4637.4 1676.89  4655.5 1676.73  4670.6 1674.62  4712.8 1673.66
  4729.1 1672.12  4793.8 1671.21  4833.5 1669.07  4872.7 1662.22  4890.8 1654.95
  4908.9 1650.36  4945.1 1645.54  4990.4 1642.01  4992.8 1641.41  4992.9 1638.48
  4993.4 1637.98  5011.9 1638.48  5026.6 1642.64  5035.4    1644  5079.2 1647.16
  5193.4 1648.23  5272.4  1650.1  5325.4 1649.09  5375.8 1650.65  5436.3 1652.98
  5485.8    1660  5600.6 1666.53    5658  1671.3  5661.6 1672.46    5750 1680.61
#Mann= 7 ,-1 , 0
  4574.1      .1       0  4729.1     .07       0  4992.9     .05       0
  5011.9     .07       0  5035.4      .1       0  5193.4    .035       0
  5375.8     .07       0
#XS Ineff= 2 , 0
                         5288.34         1650.16
Permanent Ineff=
       F       F
Bank Sta=4992.9,5011.9
XS Rating Curve= 0 ,0
Exp/Cntr=0.3,0.1

Type RM Length L Ch R = 1 ,11057   ,486,486,486
BEGIN DESCRIPTION:
North Fork Cypress Creek 21.0
END DESCRIPTION:
XS GIS Cut Line= 3
      1970106.52     13933271.26      1969573.25     13933292.13
      1969024.96     13933074.99
#Sta/Elev= 30
  4532.9 1671.24  4559.3 1667.43  4602.5 1664.21  4821.6 1662.04  4902.7 1658.68
  4953.7 1659.07  4959.7 1657.32  4966.7  1649.4  4983.3 1636.38  4983.8 1635.88
  5002.3 1636.38  5004.8  1638.4  5016.8 1640.72  5049.8 1644.25    5075 1643.98
  5132.7 1643.32  5216.3 1645.57  5313.1  1658.9  5327.7 1659.25  5335.7 1659.12
  5419.6  1670.1  5466.4 1680.55  5490.6 1684.01  5513.2 1685.16  5551.9 1692.26
  5564.4 1692.38  5592.2 1698.51    5610 1705.61  5626.1 1709.79  5656.3 1711.34
#Mann= 7 ,-1 , 0
  4532.9     .07       0  4983.3     .05       0  5002.3     .07       0
    5075    .035       0  5132.7     .07       0  5327.7      .1       0
  5466.4    .035       0
Bank Sta=4983.3,5002.3
XS Rating Curve= 0 ,0
Exp/Cntr=0.3,0.1

Type RM Length L Ch R = 1 ,10571   ,433,433,433
BEGIN DESCRIPTION:
North Fork Cypress Creek 20.0
END DESCRIPTION:
XS GIS Cut Line= 3
      1970221.24     13933211.97        1969525.       13932875.
      1969074.97       13932925.
#Sta/Elev= 30
  4221.6 1675.51  4246.3 1670.48  4395.6 1661.21  4429.6 1661.74  4462.9 1659.12
  4530.8 1659.33  4750.2 1653.96  4790.2 1652.52  4892.9  1650.4  4922.9 1645.37
  4939.5  1644.7  5002.1 1636.79  5005.2 1636.32  5006.9 1634.15  5007.4 1633.65
  5025.9 1634.15  5026.3  1636.1  5034.8 1638.27  5087.7 1643.58  5119.9 1650.72
  5145.4 1651.15  5174.2 1655.73  5213.5 1659.79  5234.6 1661.97  5254.1 1665.88
  5291.9 1678.53  5344.6 1688.16  5394.5  1703.2  5409.6 1709.46  5447.9 1710.86
#Mann= 8 ,-1 , 0
  4221.6     .07       0  4750.2      .1       0  4790.2     .07       0
  5006.9     .05       0  5025.9     .07       0  5034.8      .1       0
  5213.5     .07       0  5344.6    .035       0
Bank Sta=5006.9,5025.9
XS Rating Curve= 0 ,0
Exp/Cntr=0.3,0.1