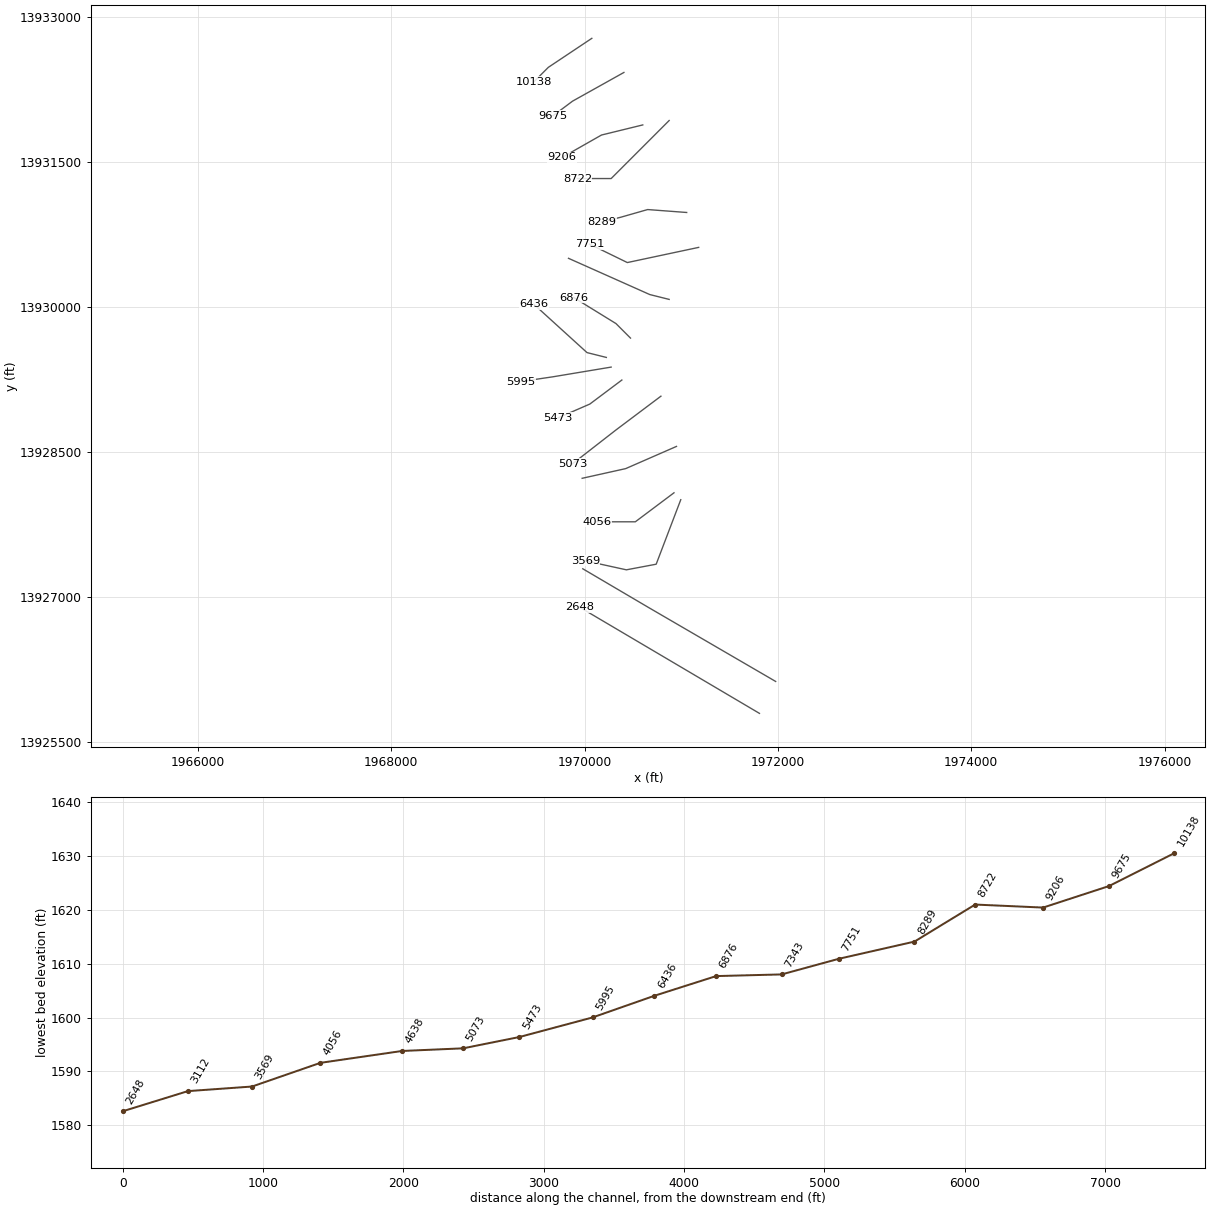
HEC-RAS study North Fork Cypress Creek.prj: North Fork Cypress Creek Base Level Engineering

--- North Fork Cypress Creek.g01 (geometry) --- (continued)

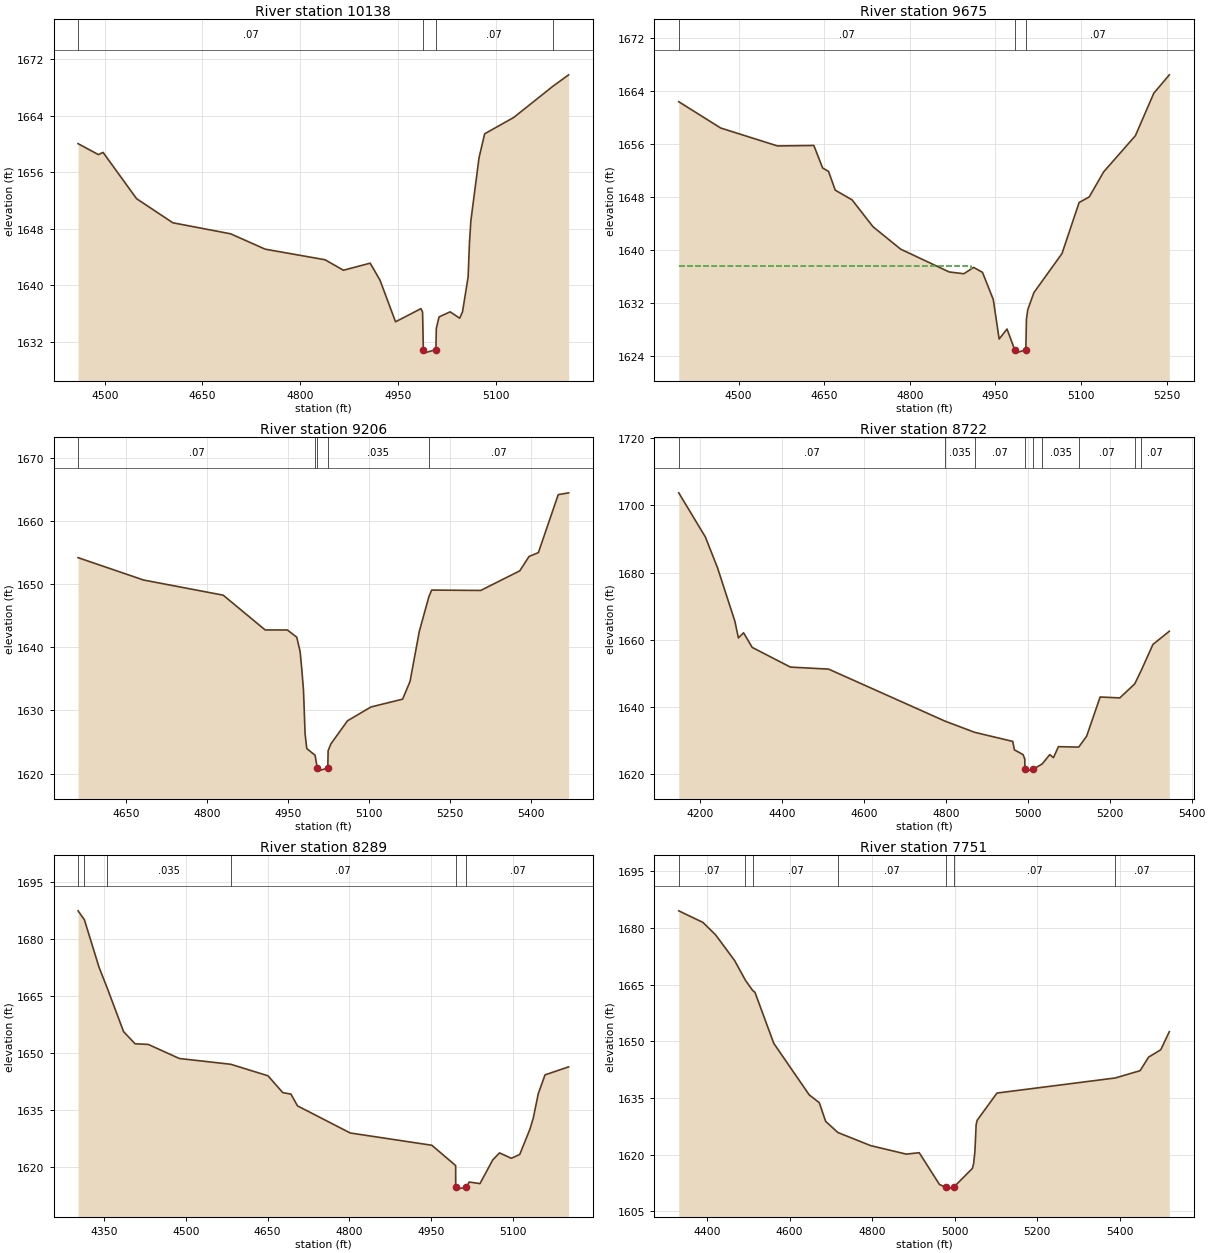
Type RM Length L Ch R = 1 ,10138   ,463,463,463
BEGIN DESCRIPTION:
North Fork Cypress Creek 19.0
END DESCRIPTION:
XS GIS Cut Line= 3
        1970075.       13932775.        1969625.       13932475.
      1969474.97     13932324.97
#Sta/Elev= 30
  4459.1 1660.04  4490.3 1658.49  4497.5  1658.8  4548.9 1652.26  4604.6 1648.85
  4693.3 1647.29  4746.3 1645.12  4838.3 1643.62  4866.4 1642.14  4907.5 1643.14
  4922.6 1640.73  4946.4 1634.85  4985.4 1636.71  4987.9 1636.24  4989.1 1630.92
  4989.6 1630.42  5008.4 1630.92    5009 1633.91  5013.2 1635.54  5030.2 1636.26
  5044.9 1635.36  5049.2 1636.26  5057.8 1641.17  5059.9 1646.08  5062.1 1649.19
  5074.6 1658.06  5083.2 1661.43  5127.8 1663.74  5187.5 1668.12  5212.1 1669.77
#Mann= 4 ,-1 , 0
  4459.1     .07       0  4989.1     .05       0  5008.4     .07       0
  5187.5    .035       0
Bank Sta=4989.1,5008.4
XS Rating Curve= 0 ,0
Exp/Cntr=0.3,0.1

Type RM Length L Ch R = 1 ,9675    ,469,469,469
BEGIN DESCRIPTION:
North Fork Cypress Creek 18.0
END DESCRIPTION:
XS GIS Cut Line= 3
      1970407.06     13932422.19        1969875.       13932125.
      1969675.03     13931975.02
#Sta/Elev= 30
  4395.2 1662.33  4468.6 1658.36  4568.2 1655.65  4631.9 1655.72  4647.2 1652.33
  4657.6  1651.8  4669.4 1648.97  4698.8 1647.51  4735.5 1643.45    4784 1640.06
  4868.9 1636.62  4894.7 1636.35  4911.8 1637.31  4927.3 1636.56  4946.2 1632.46
  4956.5 1626.49  4970.3    1628  4983.8 1624.86  4984.3 1624.36  5003.2 1624.86
  5004.3 1629.47  5006.6 1630.92  5017.4  1633.5  5066.6  1639.4  5096.6 1647.11
  5114.3 1647.95  5139.6 1651.74  5195.2  1657.2  5227.4 1663.61  5254.6 1666.39
#Mann= 3 ,-1 , 0
  4395.2     .07       0  4983.8     .05       0  5003.2     .07       0
#XS Ineff= 2 , 0
         4907.62 1637.59
Permanent Ineff=
       F       F
Bank Sta=4983.8,5003.2
XS Rating Curve= 0 ,0
Exp/Cntr=0.3,0.1

Type RM Length L Ch R = 1 ,9206    ,484,484,484
BEGIN DESCRIPTION:
North Fork Cypress Creek 17.0
END DESCRIPTION:
XS GIS Cut Line= 3
      1970602.08     13931879.53        1970175.       13931775.
      1969766.21     13931542.64
#Sta/Elev= 30
  4560.6 1654.23  4682.2 1650.68  4829.8 1648.28  4907.6 1642.77  4948.9 1642.76
  4966.2 1641.62  4972.5 1639.32  4975.6 1636.51  4978.7 1633.24  4981.7 1626.27
  4984.8 1623.96  5000.2  1622.9  5004.3 1620.88  5004.8 1620.38  5023.8 1620.88
  5024.4 1623.61  5029.5 1624.69  5060.3 1628.36  5103.8 1630.55  5162.5 1631.79
  5176.3 1634.59  5193.5 1642.52  5211.3 1648.05  5216.5 1649.09  5307.4 1649.03
  5379.9 1652.14  5397.1 1654.42  5414.4 1655.03  5451.2 1664.22  5470.5 1664.51
#Mann= 5 ,-1 , 0
  4560.6     .07       0  5000.2    .035       0  5004.3     .05       0
  5023.8    .035       0  5211.3     .07       0
Bank Sta=5004.3,5023.8
XS Rating Curve= 0 ,0
Exp/Cntr=0.3,0.1

Type RM Length L Ch R = 1 ,8722    ,433,433,433
BEGIN DESCRIPTION:
North Fork Cypress Creek 16.0
END DESCRIPTION:
XS GIS Cut Line= 3
        1970875.       13931925.        1970275.       13931325.
      1969925.03       13931325.
#Sta/Elev= 30
  4146.9 1703.76  4211.9 1690.63  4241.5  1681.5  4284.1 1665.53  4292.6 1660.58
  4305.3 1662.11  4326.4 1657.75  4419.7  1651.9    4513  1651.3  4797.8  1635.8
  4869.8 1632.49  4962.8 1629.79    4967 1627.27  4988.1 1625.85  4992.3 1624.56
  4992.7 1621.44  4993.2 1620.94  5012.2 1621.44  5034.9 1623.09  5053.4 1625.86
  5062.4 1624.95  5074.4 1628.22    5124 1628.09  5143.4 1631.33  5176.4    1643
  5224.4 1642.73  5260.9 1646.91  5276.9 1650.93  5305.4 1658.65  5345.4 1662.57
#Mann= 9 ,-1 , 0
  4146.9     .07       0  4797.8    .035       0  4869.8     .07       0
  4992.7     .05       0  5012.2     .07       0  5034.9    .035       0
    5124     .07       0  5260.9    .035       0  5276.9     .07       0
Bank Sta=4992.7,5012.2
XS Rating Curve= 0 ,0
Exp/Cntr=0.3,0.1

Type RM Length L Ch R = 1 ,8289    ,538,538,538
BEGIN DESCRIPTION:
North Fork Cypress Creek 15.0
END DESCRIPTION:
XS GIS Cut Line= 4
      1971056.32       13930974.      1970652.41     13931004.26
        1970375.       13930925.      1970175.01       13930875.
#Sta/Elev= 30
  4302.3 1687.36  4313.9 1685.02  4340.7 1672.53  4356.1  1666.9  4385.8 1655.54
  4406.9 1652.34    4431 1652.18  4488.1 1648.47  4582.3 1646.95  4650.6 1643.92
  4677.7 1639.49  4692.7  1639.1  4704.7    1636  4801.4 1628.86  4951.1 1625.62
  4994.8 1620.28  4994.9 1614.57  4995.4 1614.07  5014.6 1614.57  5019.6 1615.94
  5039.4 1615.53  5062.8 1621.76  5075.2 1623.61  5096.9 1622.19  5112.3  1623.2
  5130.9 1629.81  5137.1 1632.75  5146.3 1639.18  5158.7 1644.16    5202 1646.27
#Mann= 6 ,-1 , 0
  4302.3    .035       0  4313.9     .07       0  4356.1    .035       0
  4582.3     .07       0  4994.9     .05       0  5014.6     .07       0
Bank Sta=4994.9,5014.6
XS Rating Curve= 0 ,0
Exp/Cntr=0.3,0.1

Type RM Length L Ch R = 1 ,7751    ,408,408,408
BEGIN DESCRIPTION:
North Fork Cypress Creek 14.0
END DESCRIPTION:
XS GIS Cut Line= 3
      1971180.37     13930613.07      1970442.43      13930456.1
      1970051.36     13930646.72
#Sta/Elev= 30
  4331.1  1684.5  4389.7 1681.44  4420.4 1678.16  4466.4 1671.38  4492.9 1666.12
  4510.5 1663.41  4515.9 1662.95  4561.5 1649.46  4647.4 1635.83  4671.9 1633.76
  4687.3 1628.81    4717 1625.86  4796.7 1622.39  4882.7 1620.15  4914.2 1620.52
  4963.3 1612.12    4978 1611.39  4978.5 1610.89  4997.7 1611.39    5043 1616.36
  5046.1 1617.63  5049.2 1620.79  5052.2 1627.91  5054.6 1629.08  5102.7  1636.3
  5389.6 1640.29  5449.8 1642.22  5470.3  1645.8  5499.9 1647.76  5520.6 1652.54
#Mann= 7 ,-1 , 0
  4331.1     .07       0  4492.9    .035       0  4510.5     .07       0
    4717     .07       0    4978     .05       0  4997.7     .07       0
  5389.6     .07       0
Bank Sta=4978,4997.7
XS Rating Curve= 0 ,0
Exp/Cntr=0.3,0.1

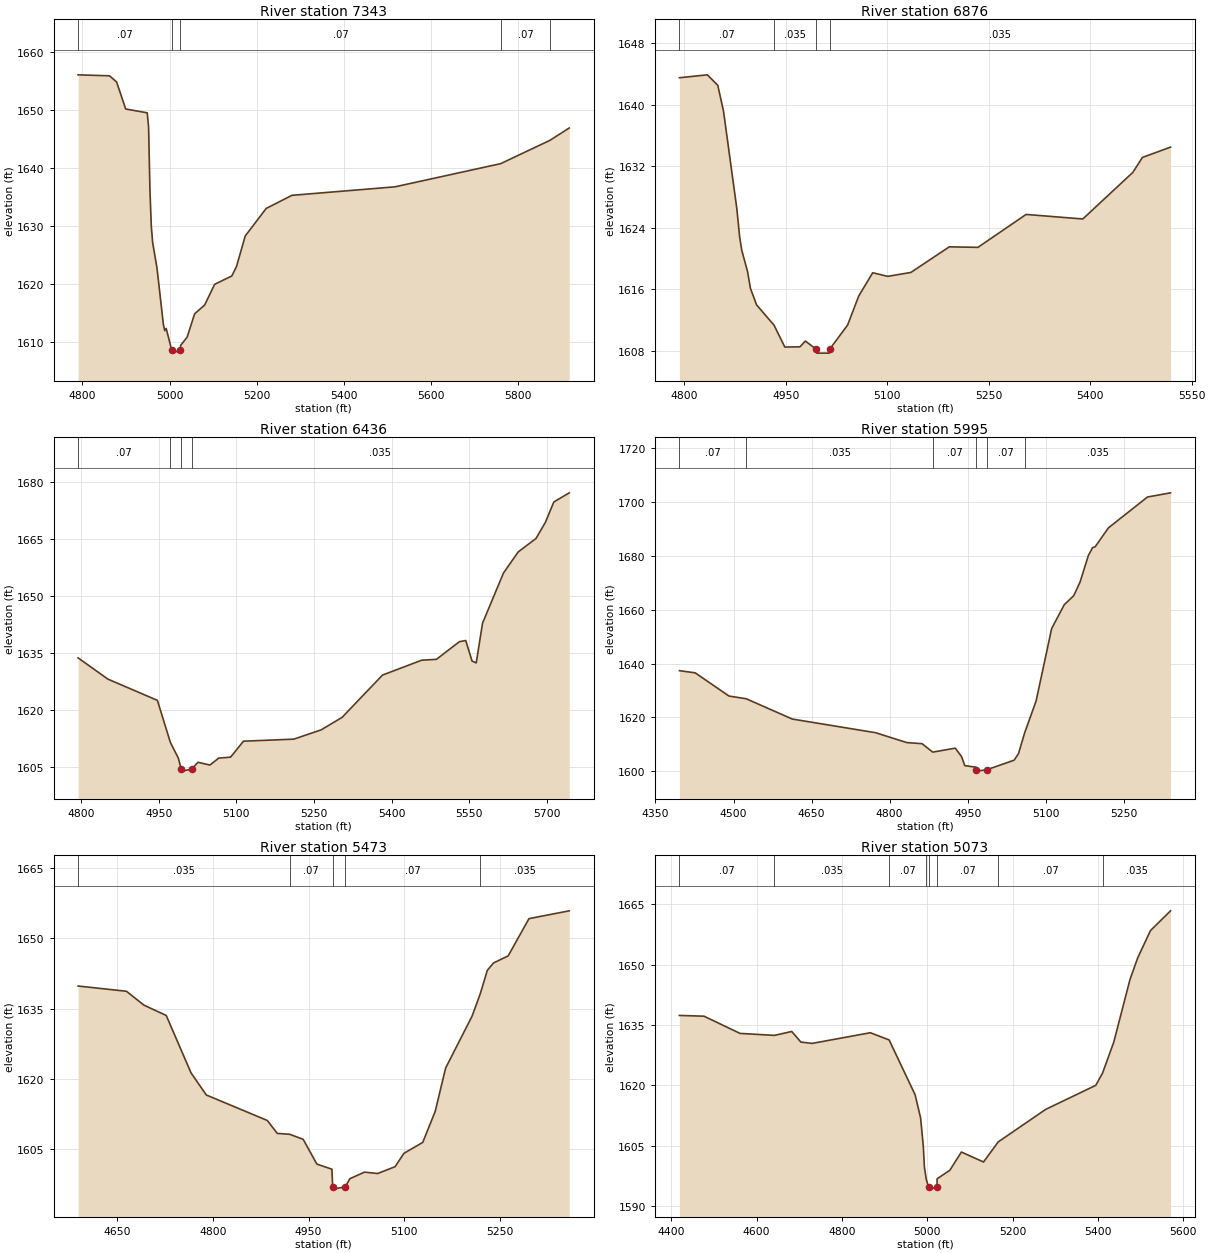
Type RM Length L Ch R = 1 ,7343    ,467,467,467
BEGIN DESCRIPTION:
North Fork Cypress Creek 13.0
END DESCRIPTION:
XS GIS Cut Line= 3
      1970875.01       13930075.        1970675.       13930125.
      1969833.66     13930500.01
#Sta/Elev= 30
    4790 1656.12  4862.2 1655.95  4878.4 1654.88  4899.3 1650.21  4948.7 1649.55
  4951.8  1647.1  4954.9  1636.2    4958 1629.98  4961.1 1627.14  4971.2 1622.65
  4985.8 1612.92  4988.9 1611.87  4992.2 1612.26  5004.9 1608.49  5005.4 1607.99
  5024.6 1608.49  5025.4 1609.34  5040.2 1610.75  5057.5 1614.79  5080.5 1616.31
  5103.4 1619.89  5142.9 1621.34  5153.8 1623.02  5173.6 1628.25  5221.7 1633.01
  5280.8 1635.28  5517.3 1636.75    5760 1640.76    5873 1644.79  5917.3 1646.93
#Mann= 5 ,-1 , 0
    4790     .07       0  5004.9     .05       0  5024.6     .07       0
    5760     .07       0    5873    .035       0
Bank Sta=5004.9,5024.6
XS Rating Curve= 0 ,0
Exp/Cntr=0.3,0.1

Type RM Length L Ch R = 1 ,6876    ,440,440,440
BEGIN DESCRIPTION:
North Fork Cypress Creek 12.0
END DESCRIPTION:
XS GIS Cut Line= 3
        1970475.       13929675.        1970325.       13929825.
       1969887.6     13930094.52
#Sta/Elev= 30
  4792.9 1643.48  4834.2 1643.86  4849.6  1642.5  4858.1 1639.13  4877.7 1626.51
    4882 1622.74  4885.1 1621.04  4893.6 1618.29  4897.8 1616.13  4906.9 1613.96
  4932.8 1611.31  4948.7 1608.47  4971.1  1608.5    4979 1609.25  4995.2 1608.18
  4995.7 1607.68  5014.4 1607.68  5014.9 1608.18  5041.5 1611.33  5057.9  1615.1
  5078.6 1618.13  5100.7 1617.66    5135 1618.17  5191.8  1621.5  5234.1 1621.43
  5305.3 1625.71  5389.1 1625.12  5463.1 1631.18  5477.2 1633.12  5518.8 1634.46
#Mann= 4 ,-1 , 0
  4792.9     .07       0  4932.8    .035       0  4995.2    .035       0
  5014.9    .035       0
Bank Sta=4995.2,5014.9
XS Rating Curve= 0 ,0
Exp/Cntr=0.3,0.1

Type RM Length L Ch R = 1 ,6436    ,441,441,441
BEGIN DESCRIPTION:
North Fork Cypress Creek 11.0
END DESCRIPTION:
XS GIS Cut Line= 3
      1970225.02     13929474.99        1970025.       13929525.
      1969474.98     13930025.01
#Sta/Elev= 30
  4794.1 1633.84  4851.8 1628.24  4947.4 1622.66  4972.5 1611.59  4987.9 1607.45
  4993.6 1604.53  4994.1 1604.03  5013.4 1604.53  5025.8 1606.36  5048.9 1605.63
    5066 1607.46  5088.9 1607.71  5113.8 1611.91  5211.1 1612.45  5263.8 1614.88
  5304.3 1618.16  5382.6 1629.31  5458.4 1633.23  5486.8 1633.45  5531.4 1638.11
  5543.5  1638.4  5555.7 1633.01  5563.8 1632.52    5576 1642.98  5616.5 1656.18
  5644.9 1661.72  5679.3 1665.26  5697.6 1669.54  5713.8 1674.87  5743.6 1677.28
#Mann= 4 ,-1 , 0
  4794.1     .07       0  4972.5    .035       0  4993.6    .035       0
  5013.4    .035       0
Bank Sta=4993.6,5013.4
XS Rating Curve= 0 ,0
Exp/Cntr=0.3,0.1

Type RM Length L Ch R = 1 ,5995    ,522,522,522
BEGIN DESCRIPTION:
North Fork Cypress Creek 10.0
END DESCRIPTION:
XS GIS Cut Line= 3
      1970275.04     13929375.01        1969675.       13929275.
      1969342.94     13929225.87
#Sta/Elev= 30
    4396 1637.34  4426.3 1636.53  4491.3 1627.91  4524.4  1626.9    4613 1619.36
    4773 1614.29    4833 1610.62  4862.4 1610.21  4882.9 1607.07  4926.2 1608.55
  4938.4 1605.37  4944.5 1602.05  4965.9 1601.48  4966.6 1600.51  4967.1 1600.01
  4986.5 1600.51  5039.4 1604.08  5047.8 1606.52  5059.5 1614.17  5081.6  1626.1
  5111.5    1653  5135.7 1661.85  5153.9 1665.21  5166.1 1670.28    5182 1680.13
    5190 1683.01  5195.2  1683.4  5220.6  1690.4  5295.6 1701.86    5340 1703.42
#Mann= 6 ,-1 , 0
    4396     .07       0  4524.4    .035       0  4882.9     .07       0
  4966.6     .05       0  4986.5     .07       0  5059.5    .035       0
Bank Sta=4966.6,4986.5
XS Rating Curve= 0 ,0
Exp/Cntr=0.3,0.1

Type RM Length L Ch R = 1 ,5473    ,400,400,400
BEGIN DESCRIPTION:
North Fork Cypress Creek 9.0
END DESCRIPTION:
XS GIS Cut Line= 3
      1970385.76     13929241.22      1970054.05     13928992.57
      1969727.01     13928850.56
#Sta/Elev= 30
  4588.2 1639.81  4664.1 1638.69  4691.6 1635.72  4726.6 1633.51  4765.4 1621.27
  4789.5 1616.51  4885.3 1611.06  4900.9 1608.29  4920.3 1608.11  4941.6 1607.03
  4963.1 1601.73  4986.7 1600.64  4987.9 1596.88  4988.4 1596.38  5007.8 1596.88
  5014.8  1598.6  5037.7 1600.01  5058.6 1599.72  5085.9 1601.18  5099.8 1604.04
  5129.3 1606.37  5148.9 1613.02  5165.2 1622.26  5206.8 1633.38  5219.6 1638.15
  5230.7 1643.17  5240.5 1644.75  5263.4 1646.25  5296.1 1654.22  5359.3 1655.89
#Mann= 5 ,-1 , 0
  4588.2    .035       0  4920.3     .07       0  4987.9     .05       0
  5007.8     .07       0  5219.6    .035       0
Bank Sta=4987.9,5007.8
XS Rating Curve= 0 ,0
Exp/Cntr=0.3,0.1

Type RM Length L Ch R = 1 ,5073    ,435,435,435
BEGIN DESCRIPTION:
North Fork Cypress Creek 8.0
END DESCRIPTION:
XS GIS Cut Line= 3
      1970789.73     13929074.11        1970325.       13928725.
      1969875.03     13928375.02
#Sta/Elev= 30
    4419 1637.38  4476.6 1637.19  4561.2 1632.92  4641.5 1632.43  4682.3  1633.4
  4703.7 1630.77  4730.1 1630.44  4866.6 1633.09  4910.6  1631.3  4971.5  1617.7
  4984.4 1611.94  4990.8 1604.83  4993.3 1599.76  4997.5  1596.8    5003 1594.79
  5003.5 1594.29  5022.9 1594.79    5023 1596.85  5052.8 1598.95    5080 1603.49
  5131.9 1601.02  5166.3    1606  5277.7 1614.08  5394.9 1620.03  5410.8 1623.04
  5437.3  1630.8  5475.3 1646.32  5493.2 1651.63  5523.2 1658.43  5570.3 1663.33
#Mann= 8 ,-1 , 0
    4419     .07       0  4641.5    .035       0  4910.6     .07       0
  4997.5     .07       0    5003     .05       0  5022.9     .07       0
  5166.3     .07       0  5410.8    .035       0
Bank Sta=5003,5022.9
XS Rating Curve= 0 ,0
Exp/Cntr=0.3,0.1

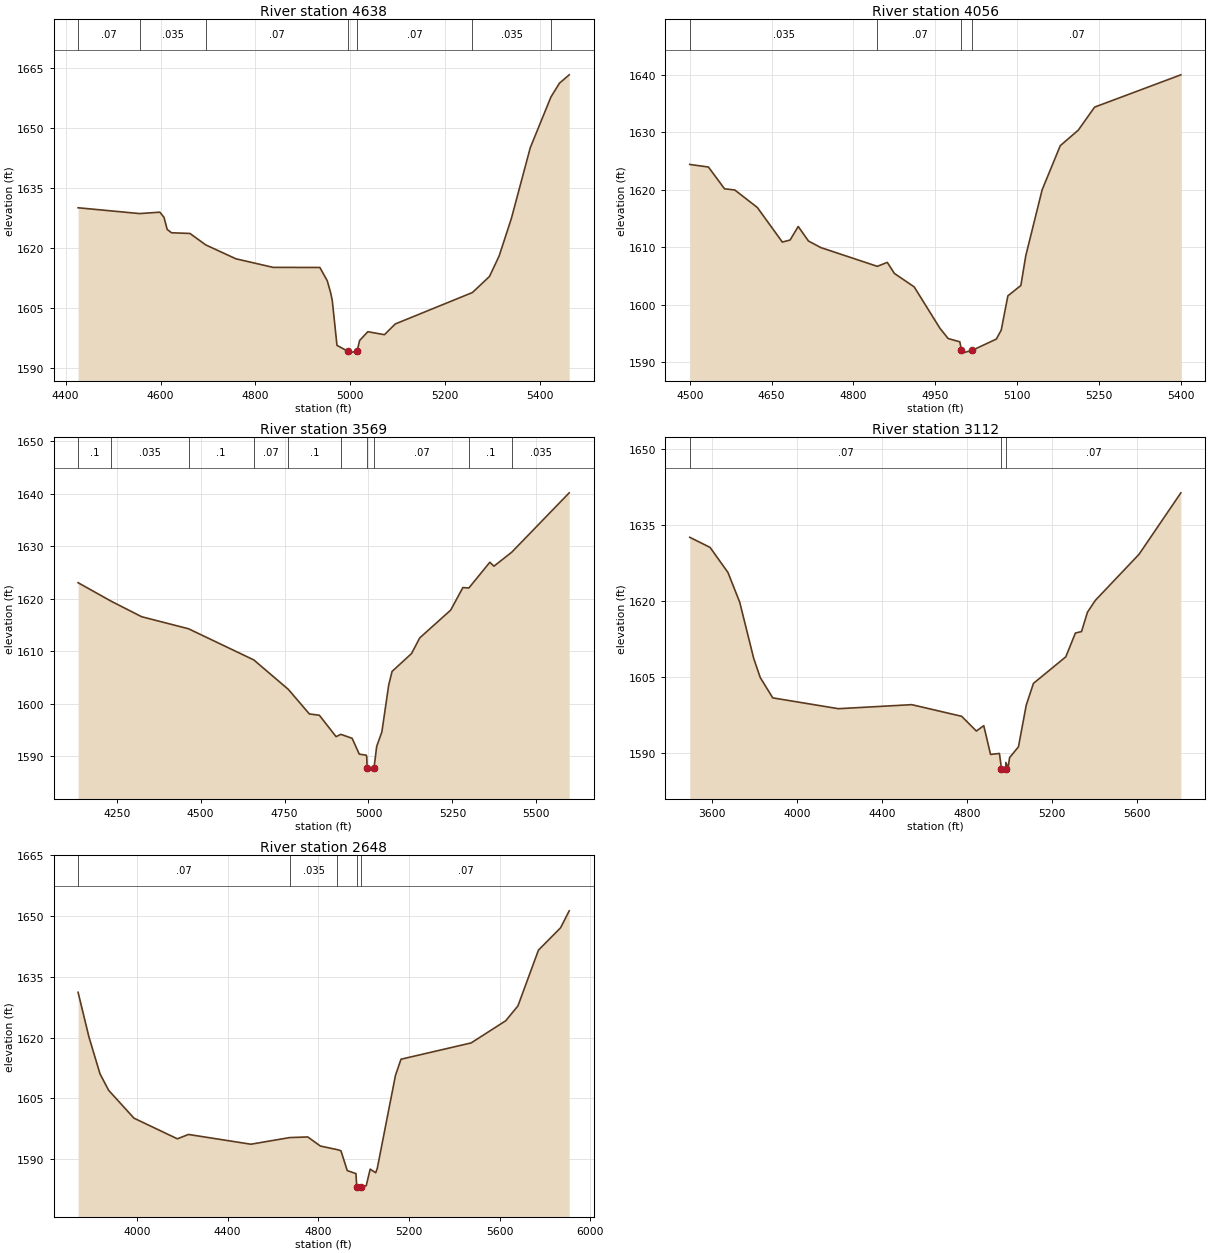
Type RM Length L Ch R = 1 ,4638    ,582,582,582
BEGIN DESCRIPTION:
North Fork Cypress Creek 7.0
END DESCRIPTION:
XS GIS Cut Line= 3
      1970950.81     13928554.68        1970425.       13928325.
      1969974.97     13928224.99
#Sta/Elev= 30
  4426.2 1630.08  4555.8 1628.63  4598.4 1628.98  4607.2 1627.69    4614 1624.66
  4623.1 1623.84  4661.9 1623.67  4695.2 1620.81  4758.8 1617.34  4837.3  1615.2
  4935.6 1615.18  4951.2 1611.87  4958.5 1608.81  4961.8  1606.9  4971.7 1595.74
  4994.1  1594.3  4994.6  1593.8  5014.1  1594.3  5019.4 1596.95  5036.7 1599.15
  5071.7  1598.4  5094.5 1601.08    5257 1608.92    5293 1612.93  5313.3 1618.03
  5339.1 1627.39    5379 1645.08  5422.5 1657.73  5440.5 1661.18    5461 1663.26
#Mann= 7 ,-1 , 0
  4426.2     .07       0  4555.8    .035       0  4695.2     .07       0
  4994.1     .05       0  5014.1     .07       0    5257    .035       0
  5422.5     .07       0
Bank Sta=4994.1,5014.1
XS Rating Curve= 0 ,0
Exp/Cntr=0.3,0.1

Type RM Length L Ch R = 1 ,4056    ,487,487,487
BEGIN DESCRIPTION:
North Fork Cypress Creek 6.0
END DESCRIPTION:
XS GIS Cut Line= 3
      1970925.02     13928075.02        1970525.       13927775.
      1970125.03       13927775.
#Sta/Elev= 30
    4500 1624.41  4534.2 1623.96  4563.8 1620.17  4582.5 1619.97  4623.8 1616.93
  4669.7 1610.91  4683.8 1611.26  4698.8 1613.62  4717.5  1611.1    4740 1609.96
  4843.7 1606.69    4862 1607.38    4875 1605.46  4911.3 1603.12  4958.5 1595.92
  4973.5 1594.14  4994.9 1593.57    4998  1592.1  4998.5  1591.6    5018  1592.1
  5061.8 1594.04  5070.8  1595.6    5083 1601.56  5106.8 1603.36  5115.8 1608.54
  5145.8    1620    5179 1627.67    5212 1630.37    5242 1634.38    5400 1639.99
#Mann= 4 ,-1 , 0
    4500    .035       0  4843.7     .07       0    4998     .05       0
    5018     .07       0
Bank Sta=4998,5018
XS Rating Curve= 0 ,0
Exp/Cntr=0.3,0.1

Type RM Length L Ch R = 1 ,3569    ,457,457,457
BEGIN DESCRIPTION:
North Fork Cypress Creek 5.0
END DESCRIPTION:
XS GIS Cut Line= 4
      1970995.06     13928003.52      1970740.75      13927336.5
       1970432.3     13927278.35      1970007.06     13927371.69
#Sta/Elev= 30
  4134.9 1623.04  4233.5 1619.52  4324.3 1616.57  4463.9 1614.28  4658.3 1608.36
  4761.2 1602.76    4824 1598.08  4853.6 1597.84  4903.6 1593.76  4917.5 1594.21
  4951.3 1593.45  4972.6 1590.44  4993.5 1590.24  4994.8 1589.94  4996.2 1587.71
  4996.7 1587.21  5016.3 1587.71  5024.5 1591.93  5039.9 1594.66  5060.3 1603.59
  5070.3 1606.17  5128.3 1609.57  5152.8 1612.55  5244.8 1617.82  5281.3 1622.12
    5299 1622.03  5361.6 1626.93  5373.8 1626.18    5427 1628.85    5598 1640.13
#Mann= 10 ,-1 , 0
  4134.9      .1       0  4233.5    .035       0  4463.9      .1       0
  4658.3     .07       0  4761.2      .1       0  4917.5     .07       0
  4996.2     .05       0  5016.3     .07       0    5299      .1       0
    5427    .035       0
Bank Sta=4996.2,5016.3
XS Rating Curve= 0 ,0
Exp/Cntr=0.3,0.1

Type RM Length L Ch R = 1 ,3112    ,464,464,464
BEGIN DESCRIPTION:
North Fork Cypress Creek 4.0
END DESCRIPTION:
XS GIS Cut Line= 3
      1971976.64     13926123.96      1970668.24     13926885.01
      1969981.48     13927289.18
#Sta/Elev= 30
  3494.1 1632.55  3589.7 1630.55  3673.9  1625.6  3729.2 1619.73  3794.9 1608.64
  3825.7 1604.85  3884.7 1600.83  4193.6 1598.69  4538.5 1599.49  4773.2 1597.19
  4842.6 1594.28  4877.3 1595.34  4909.3 1589.66    4951 1589.85  4960.7 1586.86
  4961.2 1586.36  4981.3 1586.86  4981.4 1588.07  4991.8 1586.96  4998.7 1589.02
  5040.5 1591.16  5077.1 1599.38    5111 1603.69  5263.3 1608.94  5308.5 1613.64
  5337.3 1613.93  5365.2 1617.75  5402.5  1620.1  5607.9 1629.19  5804.6 1641.33
#Mann= 3 ,-1 , 0
  3494.1     .07       0  4960.7     .05       0  4981.3     .07       0
Bank Sta=4960.7,4981.3
XS Rating Curve= 0 ,0
Exp/Cntr=0.3,0.1

Type RM Length L Ch R = 1 ,2648    ,342,342,342
BEGIN DESCRIPTION:
North Fork Cypress Creek 3.1
END DESCRIPTION:
XS GIS Cut Line= 2
      1971809.09     13925793.77      1969944.26     13926894.59
#Sta/Elev= 30
  3741.1 1631.19  3788.8 1620.21  3837.6 1611.09  3875.9 1607.01  3987.4 1600.14
    4179 1595.04  4227.8 1596.12    4503 1593.71  4674.4 1595.35  4753.8  1595.5
  4809.5 1593.26  4884.8 1592.36  4900.1  1592.1    4928  1587.2  4966.3 1586.46
  4969.9 1583.13  4970.4 1582.63  4990.6 1583.13  5011.6 1583.48    5029 1587.56
  5053.4 1586.67  5060.4 1587.77  5140.5 1610.69  5164.9 1614.68  5474.2  1618.7
  5626.5 1624.16  5680.5 1627.83    5771 1641.59  5868.6 1647.11  5906.6 1651.29
#Mann= 5 ,-1 , 0
  3741.1     .07       0  4674.4    .035       0  4884.8     .07       0
  4969.9     .05       0  4990.6     .07       0
Bank Sta=4969.9,4990.6
XS Rating Curve= 0 ,0
Exp/Cntr=0.3,0.1