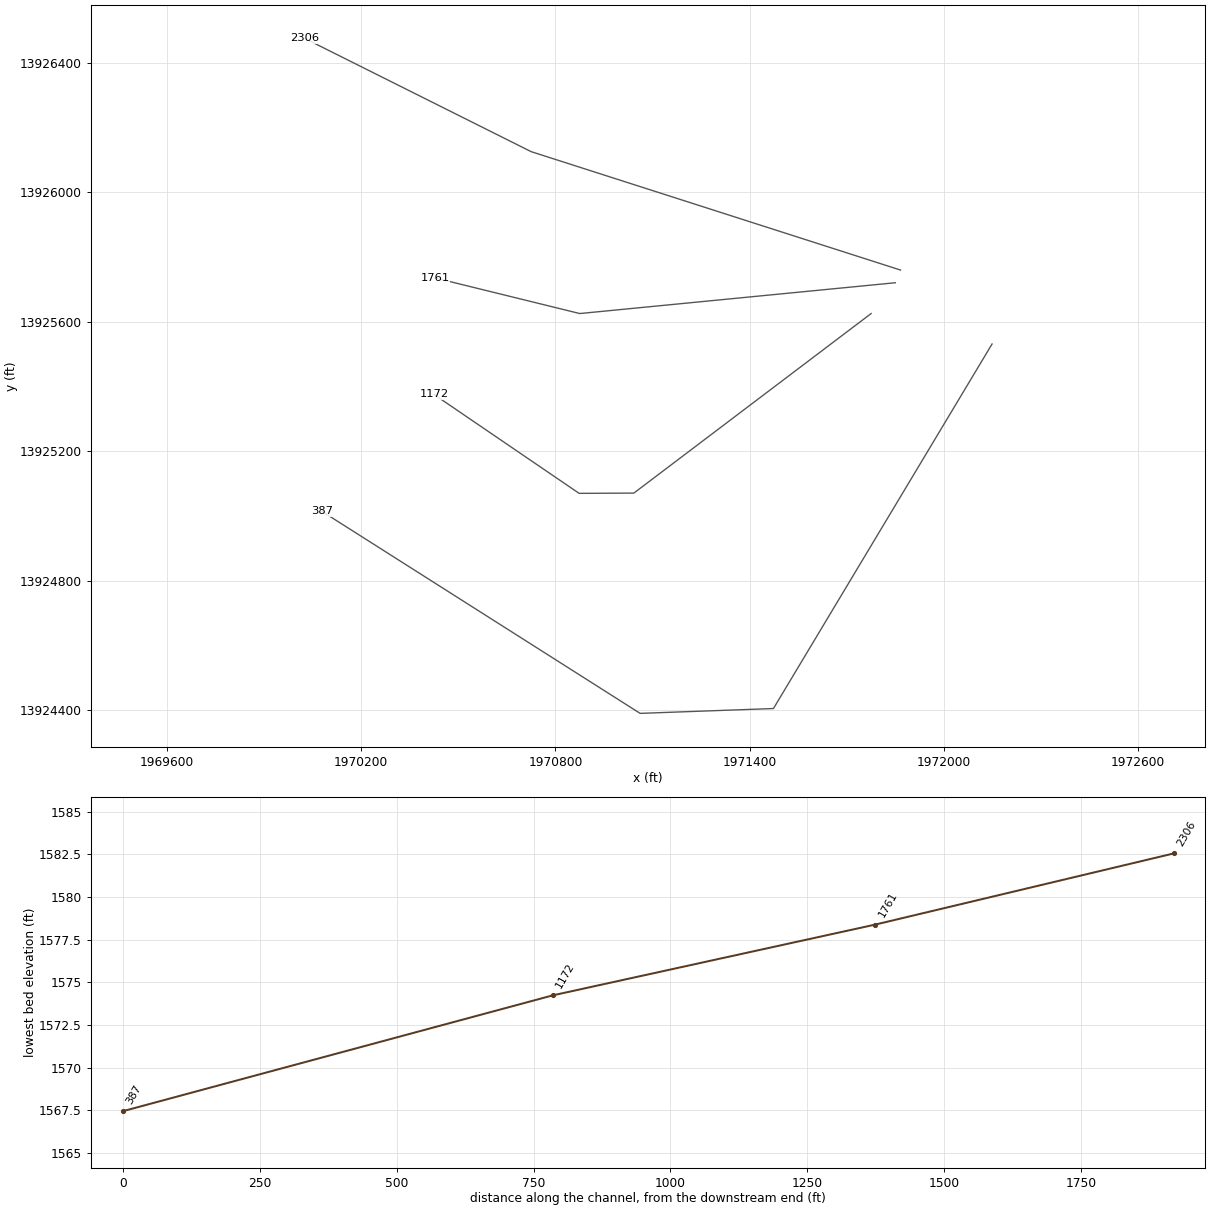
HEC-RAS study North Fork Cypress Creek.prj: North Fork Cypress Creek Base Level Engineering

--- North Fork Cypress Creek.g01 (geometry) --- (continued)

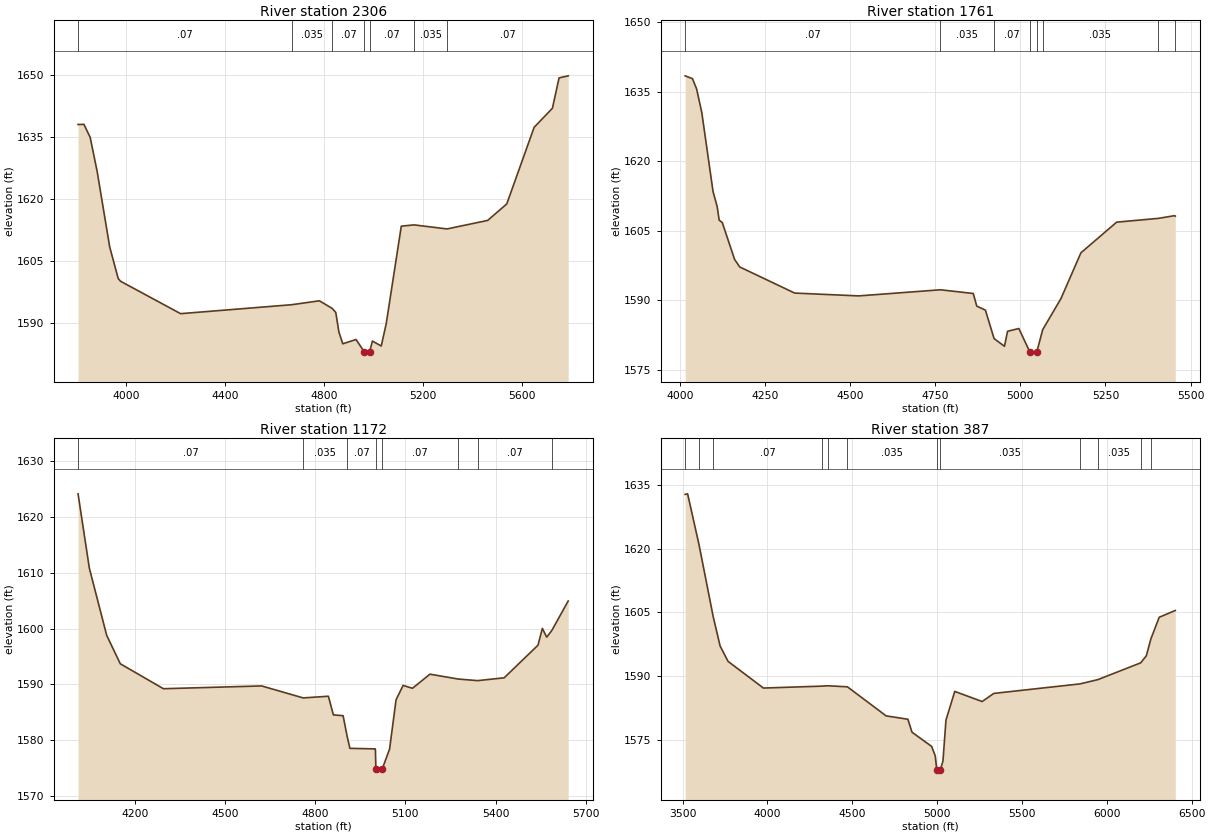
Type RM Length L Ch R = 1 ,2306    ,545,545,545
BEGIN DESCRIPTION:
North Fork Cypress Creek 3.2
END DESCRIPTION:
XS GIS Cut Line= 3
      1971865.67     13925759.33        1970725.       13926125.
      1970024.98     13926475.01
#Sta/Elev= 30
  3806.3 1638.06  3830.1 1638.09  3855.3 1634.95  3883.7 1626.65  3934.1 1608.48
  3968.7  1600.8  3978.2 1600.16  4220.7 1592.33  4669.1 1594.49  4781.5 1595.44
  4833.5 1593.59  4847.7 1592.62  4860.3 1587.89    4876 1585.05  4929.6 1586.08
  4963.3 1583.05  4963.8 1582.55    4984 1583.05  4995.7 1585.71  5031.4 1584.51
  5051.5 1589.91  5112.4 1613.48  5163.8 1613.79  5297.2 1612.81  5461.4 1614.87
  5538.6 1618.86  5649.2 1637.38    5723 1641.98  5749.9 1649.32  5786.8 1649.82
#Mann= 7 ,-1 , 0
  3806.3     .07       0  4669.1    .035       0  4833.5     .07       0
  4963.3     .05       0    4984     .07       0  5163.8    .035       0
  5297.2     .07       0
Bank Sta=4963.3,4984
XS Rating Curve= 0 ,0
Exp/Cntr=0.3,0.1

Type RM Length L Ch R = 1 ,1761    ,589,589,589
BEGIN DESCRIPTION:
North Fork Cypress Creek 2.1
END DESCRIPTION:
XS GIS Cut Line= 3
      1971849.64     13925720.14        1970875.       13925625.
      1970427.81     13925735.06
#Sta/Elev= 30
  4015.4 1638.46  4037.1 1637.84  4049.2 1635.62  4064.3 1630.56  4097.4 1613.48
  4109.5 1610.23  4115.5 1607.29  4124.5 1606.79  4160.7 1598.83  4175.8  1597.2
  4337.2 1591.56  4525.4 1590.95  4765.4 1592.27  4861.8 1591.47  4872.1 1588.74
  4897.5 1587.88  4922.9 1581.74  4953.5 1580.07  4962.5 1583.31  4995.7 1583.91
  5027.8 1578.88  5028.3 1578.38  5048.5 1578.88  5065.8 1583.67  5119.3 1590.36
    5178 1600.25    5283 1606.87  5404.7 1607.68  5453.7 1608.28  5455.2 1608.18
#Mann= 8 ,-1 , 0
  4015.4     .07       0  4765.4    .035       0  4922.9     .07       0
  5027.8     .05       0  5048.5     .07       0  5065.8    .035       0
  5404.7     .07       0  5453.7    .035       0
Bank Sta=5027.8,5048.5
XS Rating Curve= 0 ,0
Exp/Cntr=0.3,0.1

Type RM Length L Ch R = 1 ,1172    ,785,785,785
BEGIN DESCRIPTION:
North Fork Cypress Creek 1.1
END DESCRIPTION:
XS GIS Cut Line= 4
      1971775.01     13925625.01      1971042.16     13925070.44
      1970873.11     13925069.63      1970424.96     13925375.03
#Sta/Elev= 30
  4011.1 1624.18  4048.8 1610.81  4106.4 1598.78  4151.6 1593.68  4295.1  1589.2
  4621.8  1589.7  4759.9 1587.55  4843.8 1587.85  4860.5  1584.5  4892.7 1584.36
    4906 1580.71  4915.3  1578.5  4999.3  1578.4  5000.2 1578.31  5001.8 1574.73
  5002.3 1574.23  5022.5 1574.73  5047.3 1578.36  5068.9 1587.21  5092.3 1589.79
  5123.5 1589.28  5181.6 1591.81  5275.3 1590.94  5340.2 1590.65  5428.5 1591.16
    5541 1597.01  5555.5 1600.03    5570 1598.45  5587.3 1599.68  5641.5 1604.95
#Mann= 8 ,-1 , 0
  4011.1     .07       0  4759.9    .035       0    4906     .07       0
  5001.8     .05       0  5022.5     .07       0  5275.3    .035       0
  5340.2     .07       0  5587.3    .035       0
Bank Sta=5001.8,5022.5
XS Rating Curve= 0 ,0
Exp/Cntr=0.3,0.1

Type RM Length L Ch R = 1 ,387     ,0,0,0
BEGIN DESCRIPTION:
North Fork Cypress Creek 0.1
END DESCRIPTION:
XS GIS Cut Line= 4
      1972148.47     13925530.92      1971473.28     13924405.04
      1971061.55     13924390.08      1970078.98     13925013.92
#Sta/Elev= 30
  3514.9 1632.72  3529.6 1632.85  3596.7 1620.91  3680.4 1603.97    3721 1597.09
    3768 1593.47  3976.4  1587.2  4319.6 1587.65  4354.2 1587.74  4471.3 1587.49
  4699.5 1580.66  4827.7 1579.87    4852 1576.82  4967.9 1573.48  4989.1 1571.24
    4998 1567.94  4998.5 1567.44  5018.8 1567.94  5034.5 1570.07  5052.1 1579.66
    5104 1586.41  5265.5 1584.03  5333.9 1585.94  5842.4 1588.18  5948.2 1589.19
  6199.9 1593.13    6233 1594.79  6259.9 1598.76  6308.9 1603.84  6403.6 1605.43
#Mann= 12 ,-1 , 0
  3514.9     .07       0  3596.7      .1       0  3680.4     .07       0
  4319.6    .035       0  4354.2     .07       0  4471.3    .035       0
    4998    .035       0  5018.8    .035       0  5842.4     .07       0
  5948.2    .035       0  6199.9     .07       0  6259.9    .035       0
Bank Sta=4998,5018.8
XS Rating Curve= 0 ,0
Exp/Cntr=0.3,0.1

Chan Stop Cuts=-1
Use User Specified Reach Order=0
Composite Channel Slope=5