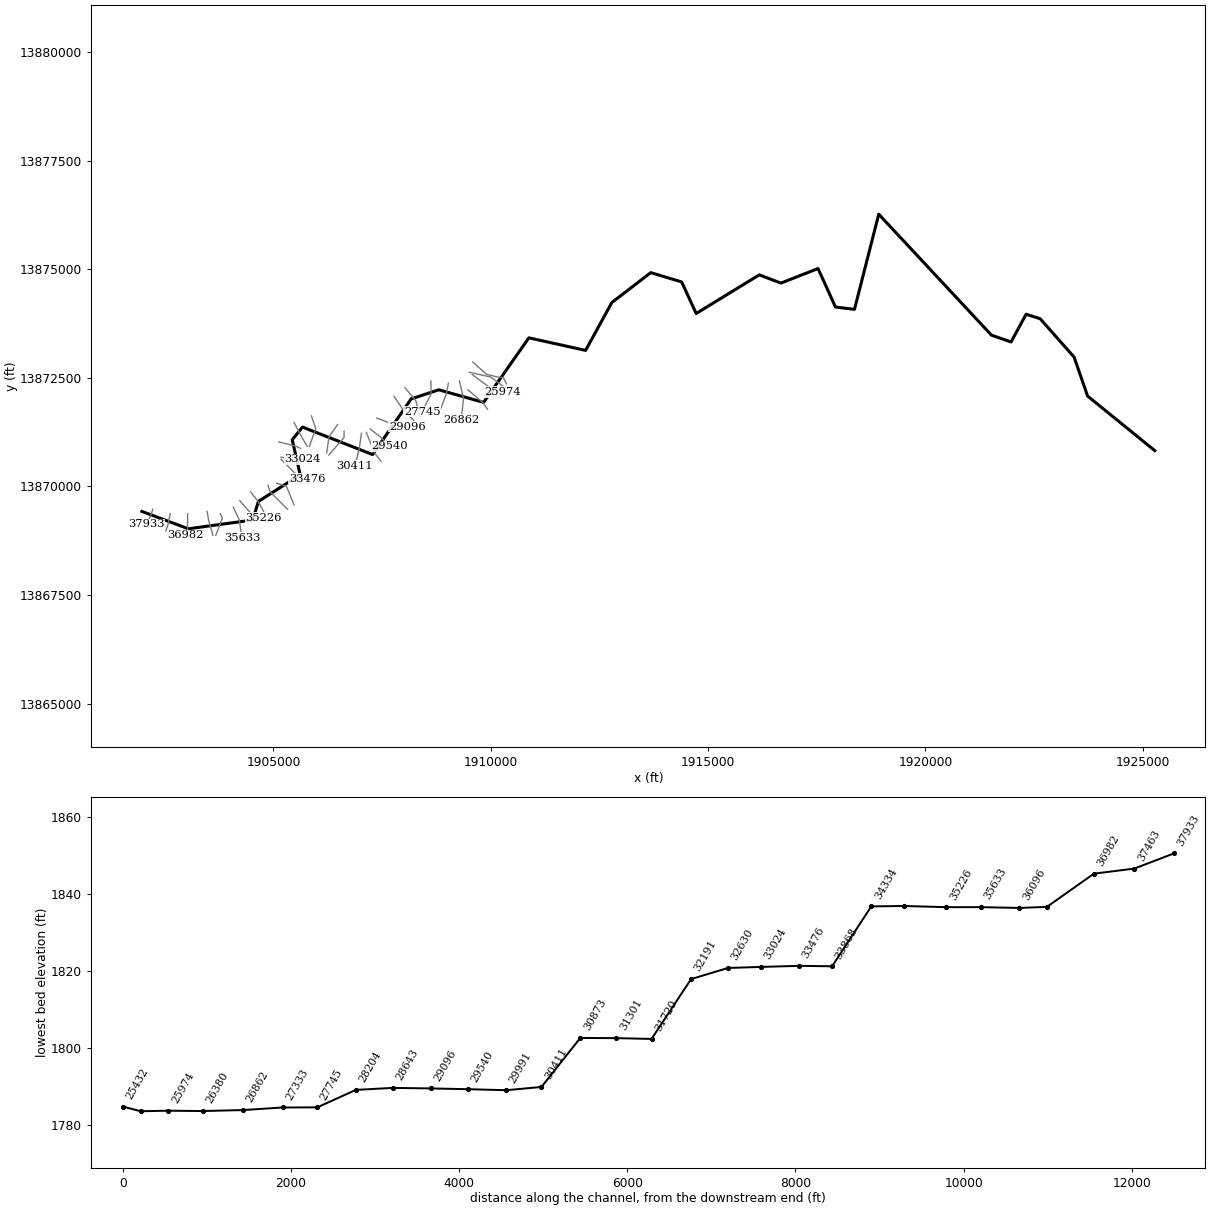
--- Palmer Creek.prj (project) ---

Proj Title=Palmer Creek Base Level Engineering
Current Plan=p01
Default Exp/Contr=0.3,0.1
English Units
Geom File=g01
Flow File=f01
Plan File=p01
BEGIN DESCRIPTION:
Palmer Creek
END DESCRIPTION:

--- Palmer Creek.p01 (plan) ---

Plan Title=Multiple Run
Short Identifier=Multiple
Geom File=g01
Flow File=f01
Subcritical Flow
K Sum by GR= 0
Std Step Tol= 0.01
Critical Tol= 0.01
Num of Std Step Trials= 20
Max Error Tol= 0.3
Flow Tol Ratio= 0.001
Split Flow NTrial= 30
Split Flow Tol= 0.02
Split Flow Ratio= 0.02
Log Output Level= 0
Friction Slope Method= 1
Unsteady Friction Slope Method= 2
Unsteady Bridges Friction Slope Method= 1
Parabolic Critical Depth
Global Vel Dist=  1 , 1 , 1
Global Log Level= 0
CheckData=True
Encroach Param= -1, 0, 0, 0
BEGIN DESCRIPTION:
Multiple Run
END DESCRIPTION:

--- Palmer Creek.f01 (steady flow) ---

Flow Title=Multiple
Number of Profiles=7
Profile Names=10-year,25-year,50-year,1pct_min,100-year,1pct_plu,500-year
River Rch & RM= Palmer Creek,Reach-1,37933
    3369    6035    8699    6045   12062   24066   22900
River Rch & RM= Palmer Creek,Reach-1,35226
    3521    6313    9107    6330   12631   25202   24001
River Rch & RM= Palmer Creek,Reach-1,33476
    4003    7237   10494    7328   14621   29173   28052
River Rch & RM= Palmer Creek,Reach-1,31301
    4187    7552   10931    7616   15196   30321   29026
River Rch & RM= Palmer Creek,Reach-1,24994
    4820    8692   12582    8761   17481   34878   33338
River Rch & RM= Palmer Creek,Reach-1,19546
    5962   10847   15787   11044   22035   43966   42432
River Rch & RM= Palmer Creek,Reach-1,10609
    6334   11540   16813   11770   23485   46859   45292
River Rch & RM= Palmer Creek,Reach-1,8891
    6667   12154   17716   12406   24752   49387   47759
River Rch & RM= Palmer Creek,Reach-1,2822
    6620   12052   17549   12275   24492   48868   47154
Boundary for River Rch & Prof#=Palmer Creek,Reach-1,1
Up Type=0
Dn Type=3
Dn Slope=0.005
Boundary for River Rch & Prof#=Palmer Creek,Reach-1,2
Up Type=0
Dn Type=3
Dn Slope=0.005
Boundary for River Rch & Prof#=Palmer Creek,Reach-1,3
Up Type=0
Dn Type=3
Dn Slope=0.005
Boundary for River Rch & Prof#=Palmer Creek,Reach-1,4
Up Type=0
Dn Type=3
Dn Slope=0.005
Boundary for River Rch & Prof#=Palmer Creek,Reach-1,5
Up Type=0
Dn Type=3
Dn Slope=0.005
Boundary for River Rch & Prof#=Palmer Creek,Reach-1,6
Up Type=0
Dn Type=3
Dn Slope=0.005
Boundary for River Rch & Prof#=Palmer Creek,Reach-1,7
Up Type=0
Dn Type=3
Dn Slope=0.005

--- Palmer Creek.g01 (geometry) ---

Geom Title=Existing Conditions

River Reach=Palmer Creek,Reach-1
Reach XY= 30
      1901975.00     13869425.00      1903043.27     13869025.18
      1904523.35     13869228.17      1904654.35     13869655.58
      1905615.87     13870268.26      1905432.09     13871075.00
      1905668.54     13871367.27      1907281.76     13870734.12
      1908168.26     13872015.87      1908804.82     13872225.30
      1909835.11     13871935.30      1910876.50     13873421.54
      1912181.19     13873132.81      1912785.50     13874234.82
      1913680.26     13874922.91      1914391.67     13874708.35
      1914725.00     13873982.07      1916176.50     13874871.39
      1916675.00     13874682.07      1917528.42     13875017.21
      1917930.11     13874130.11      1918367.05     13874078.00
      1918924.91     13876267.81      1921518.83     13873482.86
      1921969.12     13873326.96      1922314.87     13873964.68
      1922638.63     13873861.54      1923419.48     13872977.43
      1923730.16     13872080.41      1925275.00     13870825.00

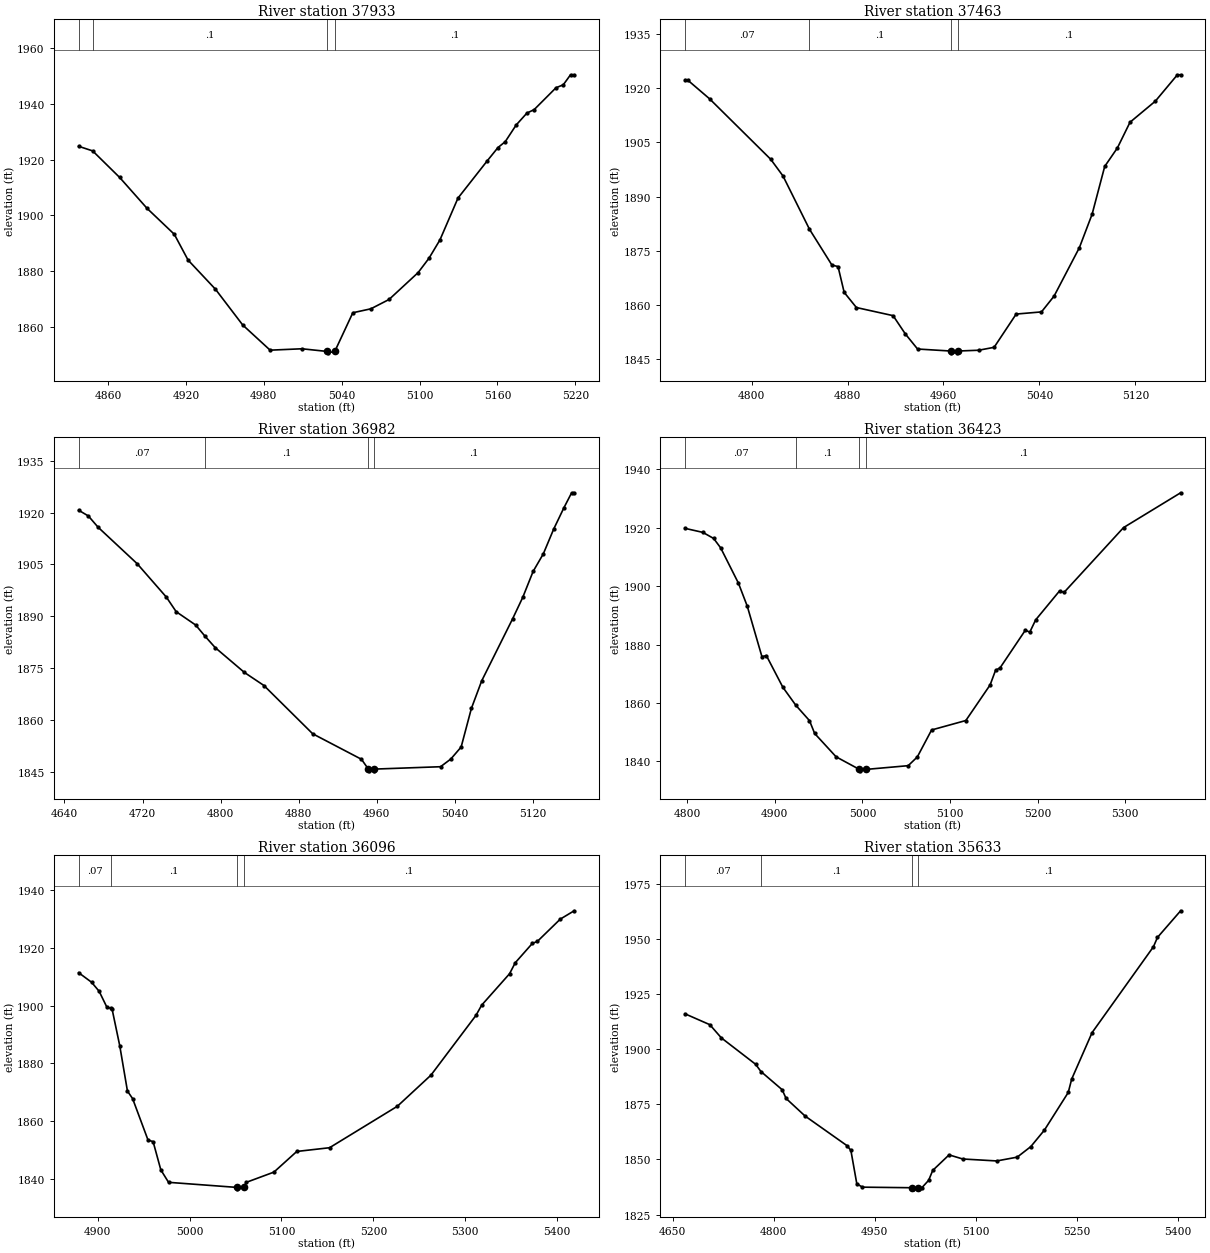
Type RM Length L Ch R = 1,37933,470,470,470
BEGIN DESCRIPTION:
Palmer Creek 75.0
END DESCRIPTION:
XS GIS Cut Line= 3
      1902224.98     13869474.95      1902175.00     13869325.00
      1902074.99     13869124.98
#Sta/Elev= 30
  4837.4 1924.83  4848.2 1923.17  4869.0 1913.63  4890.1 1902.53  4911.1 1893.21
  4921.7 1883.95  4942.8 1873.47  4963.8 1860.62  4984.9 1851.58  5009.4 1852.08
  5028.9 1851.12  5029.4 1850.62  5034.7 1851.12  5048.6 1865.02  5062.5 1866.44
  5076.5 1869.79  5098.9 1879.45  5107.3 1884.63  5115.7 1891.18  5129.6 1906.22
  5152.0 1919.52  5160.4 1924.37  5166.0 1926.48  5174.4 1932.46  5182.7 1936.76
  5188.3 1938.01  5205.1 1945.86  5210.7 1946.92  5216.3 1950.52  5219.1 1950.52
#Mann=4,-1,0
  4837.4    0.07       0  4848.2     0.1       0  5028.9    0.05       0
  5034.7     0.1       0
Bank Sta=5028.9,5034.7
Exp/Cntr=0.3,0.1

Type RM Length L Ch R = 1,37463,481,481,481
BEGIN DESCRIPTION:
Palmer Creek 74.0
END DESCRIPTION:
XS GIS Cut Line= 3
      1902625.00     13869374.99      1902575.00     13869125.00
      1902524.99     13868974.96
#Sta/Elev= 30
  4744.6 1922.20  4747.1 1922.20  4765.0 1917.11  4816.0 1900.33  4826.2 1895.72
  4848.3 1880.94  4867.0 1871.01  4872.1 1870.60  4877.2 1863.45  4887.4 1859.24
  4918.0 1856.99  4928.2 1851.92  4938.4 1847.74  4966.0 1847.18  4966.5 1846.68
  4971.3 1846.68  4971.8 1847.18  4989.3 1847.40  5002.2 1848.21  5020.6 1857.43
  5041.7 1858.03  5052.2 1862.41  5073.3 1875.85  5083.9 1885.11  5094.4 1898.36
  5105.0 1903.50  5115.5 1910.61  5136.6 1916.45  5155.0 1923.77  5157.7 1923.77
#Mann=4,-1,0
  4744.6    0.07       0  4848.3     0.1       0  4966.0    0.05       0
  4971.8     0.1       0
Bank Sta=4966,4971.8
Exp/Cntr=0.3,0.1

Type RM Length L Ch R = 1,36982,559,559,559
BEGIN DESCRIPTION:
Palmer Creek 73.0
END DESCRIPTION:
XS GIS Cut Line= 3
      1903025.00     13869375.02      1903025.00     13869025.00
      1902975.01     13868875.04
#Sta/Elev= 30
  4654.5 1920.68  4664.5 1919.01  4674.5 1915.75  4714.5 1905.23  4744.5 1895.55
  4754.5 1891.36  4774.5 1887.50  4784.0 1884.30  4794.5 1880.98  4824.5 1873.79
  4844.5 1870.02  4894.5 1856.07  4944.5 1848.70  4951.6 1845.86  4952.1 1845.36
  4957.0 1845.36  4957.5 1845.86  5025.6 1846.55  5036.1 1848.77  5046.7 1852.24
  5057.2 1863.39  5067.8 1871.38  5099.4 1889.25  5109.9 1895.51  5120.5 1902.99
  5131.0 1908.09  5141.6 1915.23  5152.1 1921.40  5160.0 1925.72  5162.6 1925.72
#Mann=4,-1,0
  4654.5    0.07       0  4784.0     0.1       0  4951.6    0.05       0
  4957.5     0.1       0
Bank Sta=4951.6,4957.5
Exp/Cntr=0.3,0.1

Type RM Length L Ch R = 1,36423,327,327,327
BEGIN DESCRIPTION:
Palmer Creek 72.0
END DESCRIPTION:
XS GIS Cut Line= 3
      1903475.00     13869424.99      1903510.37     13869217.65
      1903607.40     13868875.78
#Sta/Elev= 30
  4797.6 1919.80  4817.9 1918.42  4830.2 1916.34  4838.2 1913.12  4858.5 1901.02
  4868.6 1893.12  4885.3 1875.86  4890.4 1876.21  4909.2 1865.37  4924.0 1859.20
  4939.6 1853.94  4945.5 1849.54  4970.0 1841.54  4996.5 1837.24  4997.0 1836.74
  5004.5 1837.24  5052.3 1838.51  5062.7 1841.50  5079.0 1850.74  5118.1 1853.98
  5145.8 1866.17  5152.0 1871.17  5157.2 1872.03  5186.0 1884.91  5191.1 1884.26
  5197.8 1888.45  5225.1 1898.38  5230.2 1897.86  5298.1 1920.06  5363.3 1931.99
#Mann=4,-1,0
  4797.6    0.07       0  4924.0     0.1       0  4996.5    0.05       0
  5004.5     0.1       0
Bank Sta=4996.5,5004.5
Exp/Cntr=0.3,0.1

Type RM Length L Ch R = 1,36096,463,463,463
BEGIN DESCRIPTION:
Palmer Creek 71.0
END DESCRIPTION:
XS GIS Cut Line= 3
      1903775.01     13869374.98      1903825.00     13869275.00
      1903675.00     13868874.99
#Sta/Elev= 30
  4879.4 1911.44  4893.4 1908.15  4901.7 1905.00  4910.1 1899.49  4914.4 1899.08
  4915.7 1898.95  4924.1 1886.14  4932.5 1870.37  4938.1 1867.77  4954.9 1853.36
  4960.4 1852.85  4968.8 1843.04  4977.2 1838.72  5051.3 1836.96  5051.8 1836.46
  5059.3 1836.96  5061.5 1838.68  5091.8 1842.26  5116.7 1849.43  5152.3 1850.72
  5226.1 1865.11  5262.6 1875.89  5311.6 1896.64  5317.8 1900.19  5348.1 1911.07
  5354.3 1914.89  5373.0 1921.63  5378.3 1922.27  5403.3 1930.03  5418.4 1932.92
#Mann=4,-1,0
  4879.4    0.07       0  4914.4     0.1       0  5051.3    0.05       0
  5059.3     0.1       0
Bank Sta=5051.3,5059.3
Exp/Cntr=0.3,0.1

Type RM Length L Ch R = 1,35633,407,407,407
BEGIN DESCRIPTION:
Palmer Creek 70.0
END DESCRIPTION:
XS GIS Cut Line= 3
      1904075.01     13869524.98      1904212.37     13869238.47
      1904275.00     13868825.02
#Sta/Elev= 30
  4668.2 1916.16  4704.9 1911.24  4722.0 1905.25  4772.9 1893.26  4780.8 1889.97
  4812.3 1881.71  4818.2 1877.72  4846.4 1869.74  4908.8 1856.25  4914.4 1854.13
  4923.2 1838.96  4931.5 1837.43  5005.6 1837.17  5006.1 1836.67  5013.7 1837.17
  5019.8 1837.18  5029.9 1840.55  5035.9 1845.02  5060.2 1852.10  5080.5 1850.23
  5131.0 1849.34  5161.4 1851.07  5181.6 1855.86  5201.8 1863.35  5237.2 1880.46
  5242.3 1886.53  5272.6 1907.64  5363.7 1946.64  5369.7 1950.88  5404.1 1962.98
#Mann=4,-1,0
  4668.2    0.07       0  4780.8     0.1       0  5005.6    0.05       0
  5013.7     0.1       0
Bank Sta=5005.6,5013.7
Exp/Cntr=0.3,0.1

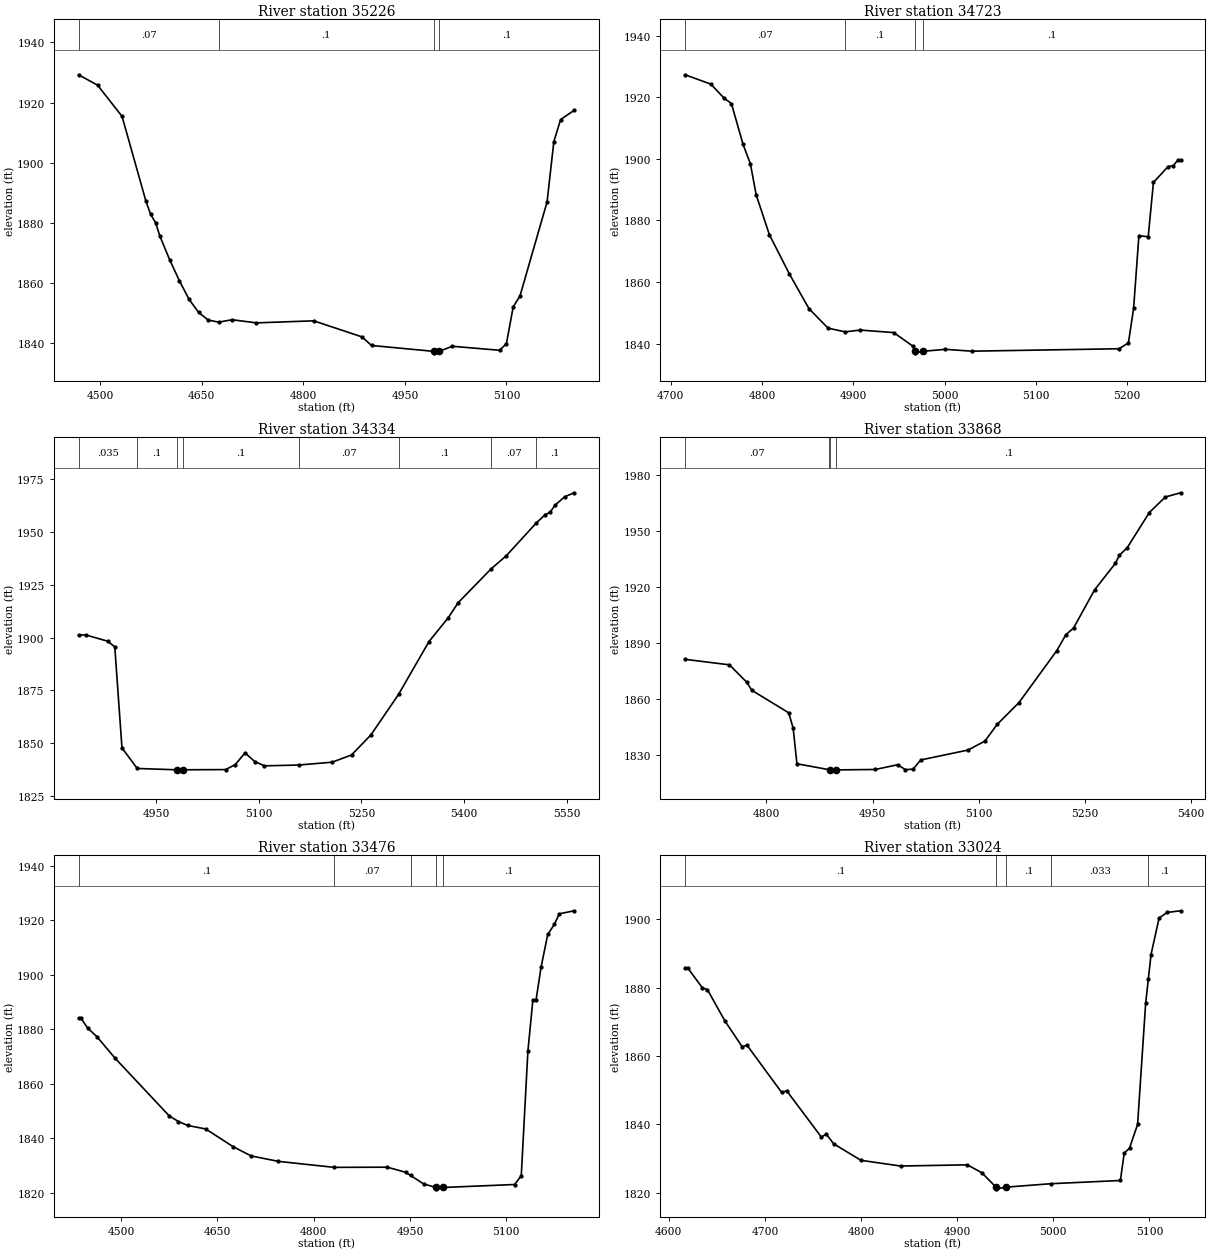
Type RM Length L Ch R = 1,35226,503,503,503
BEGIN DESCRIPTION:
Palmer Creek 69.0
END DESCRIPTION:
XS GIS Cut Line= 3
      1904224.98     13869675.02      1904575.00     13869275.00
      1904774.96     13869275.00
#Sta/Elev= 30
  4468.4 1929.25  4496.4 1925.78  4532.5 1915.40  4567.6 1887.25  4574.7 1882.75
  4581.9 1880.04  4588.5 1875.44  4602.7 1867.69  4617.0 1860.72  4631.2 1854.55
  4645.4 1850.15  4659.7 1847.56  4675.4 1846.88  4694.8 1847.68  4730.9 1846.64
  4815.3 1847.32  4886.5 1841.99  4900.8 1839.11  4992.3 1837.16  4992.8 1836.66
  5000.9 1837.16  5019.9 1838.85  5089.9 1837.51  5099.9 1839.74  5109.9 1851.98
  5119.9 1855.59  5159.9 1886.92  5169.9 1907.01  5179.9 1914.34  5199.9 1917.41
#Mann=4,-1,0
  4468.4    0.07       0  4675.4     0.1       0  4992.3    0.05       0
  5000.9     0.1       0
Bank Sta=4992.3,5000.9
Exp/Cntr=0.3,0.1

Type RM Length L Ch R = 1,34723,389,389,389
BEGIN DESCRIPTION:
Palmer Creek 68.0
END DESCRIPTION:
XS GIS Cut Line= 3
      1904474.98     13869875.03      1904650.23     13869650.20
      1904774.99     13869425.01
#Sta/Elev= 30
  4715.9 1927.35  4744.0 1924.32  4758.5 1919.79  4766.6 1918.01  4779.3 1904.77
  4787.4 1898.39  4793.7 1888.34  4808.2 1875.35  4830.0 1862.65  4851.6 1851.29
  4872.4 1845.00  4891.1 1843.79  4907.7 1844.37  4944.2 1843.56  4965.6 1839.08
  4967.6 1837.47  4968.1 1836.97  4976.3 1837.47  5000.8 1838.11  5029.8 1837.51
  5190.9 1838.30  5201.2 1840.18  5206.9 1851.39  5212.7 1875.05  5222.9 1874.70
  5228.6 1892.35  5244.7 1897.53  5250.4 1897.82  5255.6 1899.72  5258.4 1899.72
#Mann=4,-1,0
  4715.9    0.07       0  4891.1     0.1       0  4967.6    0.05       0
  4976.3     0.1       0
Bank Sta=4967.6,4976.3
Exp/Cntr=0.3,0.1

Type RM Length L Ch R = 1,34334,466,466,466
BEGIN DESCRIPTION:
Palmer Creek 67.0
END DESCRIPTION:
XS GIS Cut Line= 3
      1904874.99     13870025.04      1904925.00     13869875.00
      1905324.97     13869475.03
#Sta/Elev= 30
  4837.0 1901.21  4847.6 1901.19  4879.2 1898.26  4889.8 1895.59  4900.3 1847.73
  4922.6 1837.98  4980.3 1837.36  4980.8 1836.86  4989.0 1837.36  5051.7 1837.45
  5065.9 1839.84  5080.0 1845.38  5094.2 1841.28  5108.3 1839.22  5158.2 1839.61
  5207.3 1840.95  5235.6 1844.38  5263.9 1853.87  5304.3 1873.07  5348.7 1898.05
  5377.0 1909.40  5391.1 1916.38  5439.2 1932.42  5461.9 1938.79  5505.5 1954.25
  5518.4 1958.17  5525.5 1959.23  5532.6 1962.57  5546.7 1966.61  5560.8 1968.53
#Mann=8,-1,0
  4837.0   0.035       0  4922.6     0.1       0  4980.3    0.05       0
  4989.0     0.1       0  5158.2    0.07       0  5304.3     0.1       0
  5439.2    0.07       0  5505.5     0.1       0
Bank Sta=4980.3,4989
Exp/Cntr=0.3,0.1

Type RM Length L Ch R = 1,33868,392,392,392
BEGIN DESCRIPTION:
Palmer Creek 66.0
END DESCRIPTION:
XS GIS Cut Line= 3
      1905075.00     13870075.00      1905298.56     13870006.63
      1905475.01     13869574.98
#Sta/Elev= 30
  4685.1 1881.22  4747.8 1878.26  4772.3 1868.87  4779.2 1864.61  4831.5 1852.49
  4837.8 1844.18  4843.1 1825.11  4888.8 1821.91  4889.9 1821.81  4890.4 1821.31
  4898.6 1821.81  4953.8 1822.04  4985.5 1824.59  4996.3 1821.96  5007.2 1822.21
  5017.9 1827.14  5084.7 1832.47  5108.7 1837.28  5125.9 1846.21  5156.7 1857.93
  5210.2 1885.87  5223.1 1894.47  5233.9 1898.02  5263.6 1918.52  5293.0 1932.81
  5298.7 1937.15  5309.6 1941.11  5341.0 1960.10  5363.6 1968.44  5385.2 1970.70
#Mann=4,-1,0
  4685.1    0.07       0  4888.8     0.1       0  4889.9    0.05       0
  4898.6     0.1       0
Bank Sta=4889.9,4898.6
Exp/Cntr=0.3,0.1

Type RM Length L Ch R = 1,33476,452,452,452
BEGIN DESCRIPTION:
Palmer Creek 65.0
END DESCRIPTION:
XS GIS Cut Line= 3
      1905175.02     13870624.98      1905575.00     13870225.00
      1905774.98     13870175.00
#Sta/Elev= 30
  4433.9 1884.16  4437.4 1884.16  4448.0 1880.47  4462.2 1877.36  4490.4 1869.48
  4575.3 1848.15  4589.4 1846.16  4603.6 1844.72  4631.9 1843.41  4674.3 1836.94
  4702.6 1833.52  4745.0 1831.52  4831.8 1829.32  4914.7 1829.38  4943.0 1827.53
  4951.0 1826.33  4971.3 1823.21  4990.6 1821.93  4991.1 1821.43  5001.4 1821.93
  5112.9 1823.02  5123.3 1826.26  5133.6 1871.91  5141.3 1890.62  5146.4 1890.90
  5154.2 1902.91  5164.5 1914.85  5174.8 1918.55  5182.5 1922.44  5205.7 1923.56
#Mann=5,-1,0
  4433.9     0.1       0  4831.8    0.07       0  4951.0     0.1       0
  4990.6    0.05       0  5001.4     0.1       0
Bank Sta=4990.6,5001.4
Exp/Cntr=0.3,0.1

Type RM Length L Ch R = 1,33024,394,394,394
BEGIN DESCRIPTION:
Palmer Creek 64.0
END DESCRIPTION:
XS GIS Cut Line= 4
      1905174.97     13870675.01      1905459.87     13870603.78
      1905618.99     13870597.00      1905675.04     13870625.02
#Sta/Elev= 30
  4616.9 1885.80  4619.5 1885.80  4635.0 1879.88  4640.1 1879.43  4658.2 1870.30
  4676.2 1862.74  4681.4 1863.12  4717.4 1849.33  4722.6 1849.83  4758.7 1836.28
  4763.8 1837.18  4771.5 1834.31  4799.9 1829.49  4841.1 1827.82  4910.6 1828.17
  4925.7 1825.85  4940.3 1821.65  4940.8 1821.15  4951.1 1821.65  4997.5 1822.65
  5069.8 1823.59  5073.8 1831.57  5079.3 1833.07  5087.7 1839.97  5096.1 1875.41
  5098.9 1882.54  5101.7 1889.67  5110.1 1900.35  5118.5 1901.98  5132.5 1902.46
#Mann=5,-1,0
  4616.9     0.1       0  4940.3   0.033       0  4951.1     0.1       0
  4997.5   0.033       0  5098.9     0.1       0
Bank Sta=4940.3,4951.1
Exp/Cntr=0.3,0.1

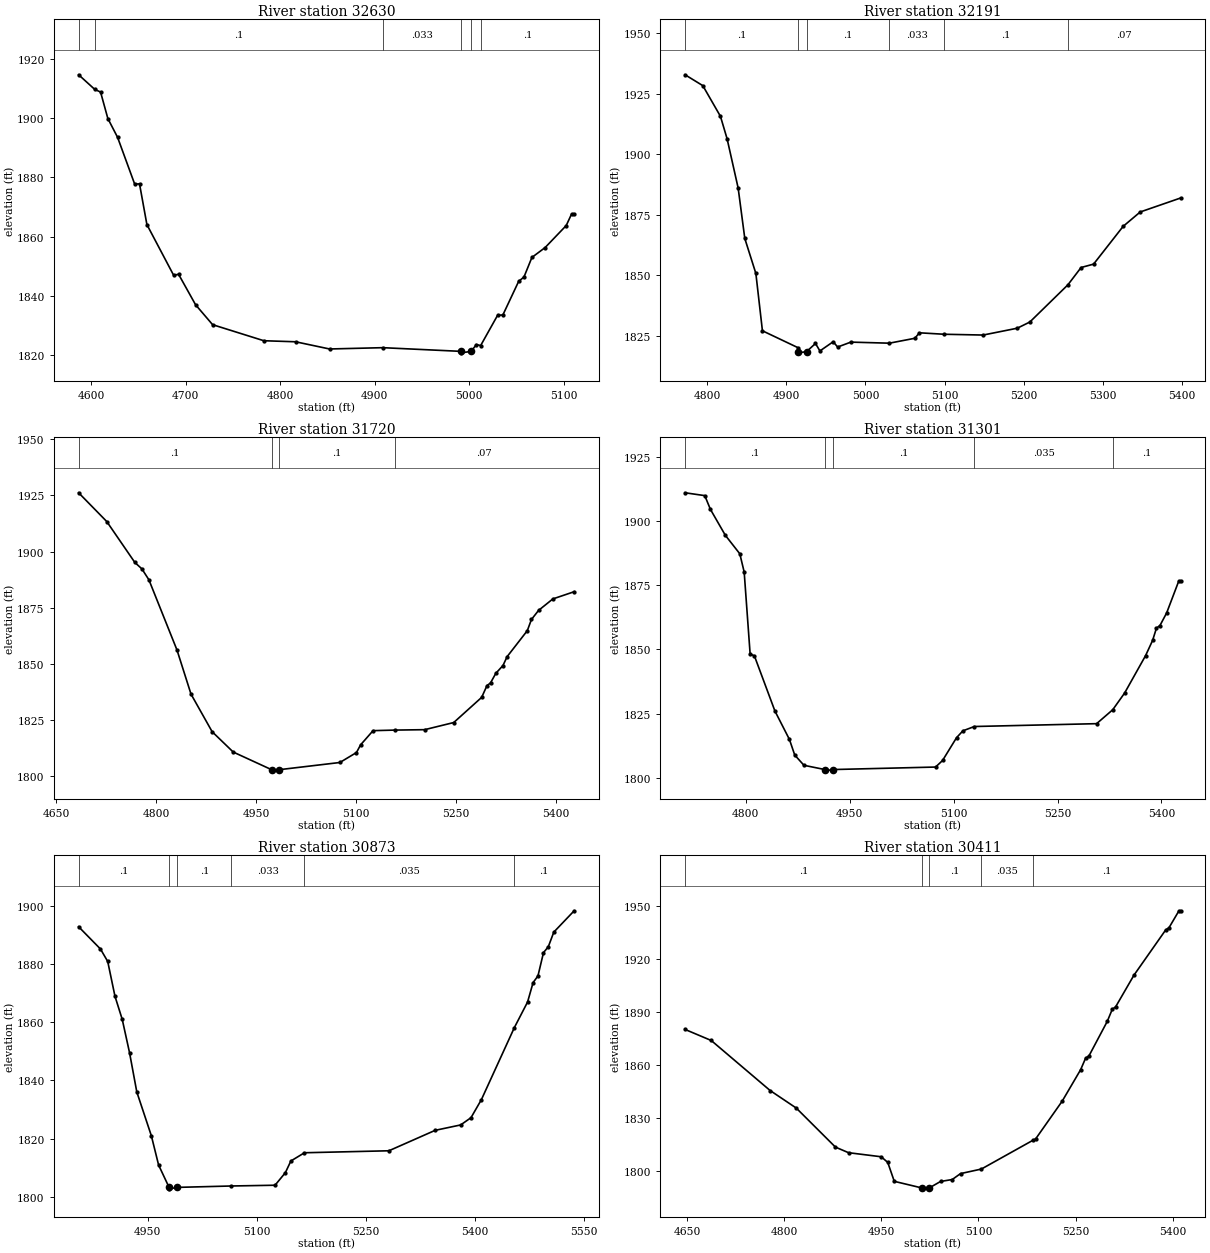
Type RM Length L Ch R = 1,32630,439,439,439
BEGIN DESCRIPTION:
Palmer Creek 63.0
END DESCRIPTION:
XS GIS Cut Line= 3
      1905124.99     13871025.00      1905525.00     13870925.00
      1905624.98     13870875.01
#Sta/Elev= 30
  4586.8 1914.60  4603.9 1909.66  4610.0 1908.78  4617.7 1899.86  4628.0 1893.51
  4646.1 1877.73  4651.2 1877.84  4659.0 1864.11  4687.3 1847.02  4692.5 1847.36
  4710.5 1837.08  4728.5 1830.37  4782.7 1824.96  4816.2 1824.61  4852.2 1822.18
  4908.5 1822.62  4991.1 1821.38  4991.6 1820.88  5001.9 1821.38  5007.5 1823.67
  5012.0 1823.34  5029.9 1833.53  5035.5 1833.65  5052.2 1844.98  5057.8 1846.43
  5066.2 1853.04  5080.2 1856.37  5102.5 1863.79  5108.1 1867.63  5110.9 1867.63
#Mann=6,-1,0
  4586.8    0.07       0  4603.9     0.1       0  4908.5   0.033       0
  4991.1   0.033       0  5001.9   0.033       0  5012.0     0.1       0
Bank Sta=4991.1,5001.9
Exp/Cntr=0.3,0.1

Type RM Length L Ch R = 1,32191,471,471,471
BEGIN DESCRIPTION:
Palmer Creek 62.0
END DESCRIPTION:
XS GIS Cut Line= 3
      1905475.00     13871475.01      1905575.00     13871275.00
      1905774.99     13870925.02
#Sta/Elev= 30
  4771.9 1932.89  4794.3 1928.40  4816.6 1915.73  4825.0 1906.46  4839.0 1886.09
  4847.4 1865.25  4861.4 1850.79  4869.7 1827.10  4914.5 1820.15  4914.6 1818.49
  4915.1 1817.99  4925.5 1818.49  4936.8 1821.86  4942.4 1818.77  4959.2 1822.58
  4964.8 1820.39  4981.5 1822.42  5030.2 1821.98  5062.5 1824.01  5068.2 1826.27
  5099.4 1825.67  5148.8 1825.34  5192.0 1828.17  5207.9 1830.73  5256.0 1846.09
  5272.7 1853.25  5288.5 1854.65  5325.9 1870.26  5347.5 1876.20  5398.6 1881.98
#Mann=6,-1,0
  4771.9     0.1       0  4914.6    0.05       0  4925.5     0.1       0
  5030.2   0.033       0  5099.4     0.1       0  5256.0    0.07       0
Bank Sta=4914.6,4925.5
Exp/Cntr=0.3,0.1

Type RM Length L Ch R = 1,31720,419,419,419
BEGIN DESCRIPTION:
Palmer Creek 61.0
END DESCRIPTION:
XS GIS Cut Line= 3
      1905875.00     13871624.99      1905975.00     13871325.00
      1905825.01     13870925.01
#Sta/Elev= 30
  4684.1 1926.12  4726.3 1913.33  4768.4 1895.14  4779.0 1892.28  4789.5 1887.43
  4831.7 1856.15  4852.7 1836.56  4884.4 1819.85  4916.0 1810.81  4973.7 1802.95
  4974.2 1802.45  4984.7 1802.95  5076.0 1806.16  5100.9 1810.59  5107.1 1814.01
  5125.8 1820.32  5158.0 1820.57  5203.2 1820.76  5246.8 1823.93  5288.7 1835.12
  5296.7 1840.36  5302.0 1841.55  5310.0 1845.84  5320.7 1849.29  5326.9 1853.23
  5357.2 1864.80  5363.4 1869.76  5374.1 1873.81  5395.5 1878.91  5427.5 1882.12
#Mann=4,-1,0
  4684.1     0.1       0  4973.7    0.05       0  4984.7     0.1       0
  5158.0    0.07       0
Bank Sta=4973.7,4984.7
Exp/Cntr=0.3,0.1

Type RM Length L Ch R = 1,31301,428,428,428
BEGIN DESCRIPTION:
Palmer Creek 60.0
END DESCRIPTION:
XS GIS Cut Line= 3
      1906475.01     13871425.02      1906278.91     13871142.65
      1906225.00     13870774.97
#Sta/Elev= 30
  4712.3 1911.12  4740.7 1910.01  4748.9 1904.63  4770.4 1894.53  4791.3 1887.32
  4797.6 1880.20  4806.2 1848.19  4812.3 1847.54  4842.0 1825.98  4862.9 1814.92
  4870.6 1808.81  4883.9 1804.82  4914.1 1803.16  4914.6 1802.66  4925.3 1803.16
  5073.9 1804.14  5084.0 1806.70  5104.2 1815.60  5113.4 1818.28  5129.9 1819.95
  5306.4 1821.06  5329.7 1826.50  5346.8 1833.00  5377.1 1847.61  5387.2 1853.52
  5392.8 1858.34  5397.8 1859.32  5407.5 1864.25  5425.1 1876.77  5427.7 1876.77
#Mann=5,-1,0
  4712.3     0.1       0  4914.1    0.05       0  4925.3     0.1       0
  5129.9   0.035       0  5329.7     0.1       0
Bank Sta=4914.1,4925.3
Exp/Cntr=0.3,0.1

Type RM Length L Ch R = 1,30873,462,462,462
BEGIN DESCRIPTION:
Palmer Creek 59.0
END DESCRIPTION:
XS GIS Cut Line= 3
      1906625.00     13871275.00      1906625.00     13871125.00
      1906275.01     13870725.01
#Sta/Elev= 30
  4855.1 1892.77  4885.1 1885.13  4895.1 1880.85  4905.1 1868.87  4915.1 1860.91
  4925.1 1849.51  4935.1 1836.00  4955.1 1820.96  4965.1 1810.88  4979.5 1803.21
  4980.0 1802.71  4990.7 1803.21  5065.2 1803.69  5125.2 1803.95  5139.4 1808.26
  5147.0 1812.28  5165.7 1815.11  5281.8 1815.79  5345.4 1822.81  5380.5 1824.67
  5394.7 1827.16  5409.0 1833.36  5454.4 1858.15  5472.5 1866.90  5480.1 1873.58
  5486.8 1875.88  5494.4 1883.88  5501.0 1885.89  5508.6 1890.93  5536.6 1898.26
#Mann=6,-1,0
  4855.1     0.1       0  4979.5    0.05       0  4990.7     0.1       0
  5065.2   0.033       0  5165.7   0.035       0  5454.4     0.1       0
Bank Sta=4979.5,4990.7
Exp/Cntr=0.3,0.1

Type RM Length L Ch R = 1,30411,420,420,420
BEGIN DESCRIPTION:
Palmer Creek 58.0
END DESCRIPTION:
XS GIS Cut Line= 3
      1907025.00     13871225.03      1906975.00     13870875.00
      1906875.00     13870475.00
#Sta/Elev= 30
  4646.6 1880.28  4687.0 1874.03  4778.0 1845.69  4818.4 1835.75  4879.0 1813.61
  4899.2 1810.46  4949.7 1808.15  4959.8 1804.97  4969.9 1794.23  5012.6 1790.48
  5013.1 1789.98  5023.9 1790.48  5041.4 1794.15  5059.5 1795.26  5072.3 1798.61
  5104.5 1801.19  5184.4 1817.53  5188.3 1818.22  5229.5 1839.70  5257.9 1857.46
  5265.6 1864.00  5270.8 1865.29  5299.1 1884.87  5306.8 1891.67  5312.0 1893.08
  5340.3 1911.01  5389.3 1936.62  5394.5 1937.92  5409.9 1947.52  5412.5 1947.52
#Mann=5,-1,0
  4646.6     0.1       0  5012.6    0.05       0  5023.9     0.1       0
  5104.5   0.035       0  5184.4     0.1       0
Bank Sta=5012.6,5023.9
Exp/Cntr=0.3,0.1

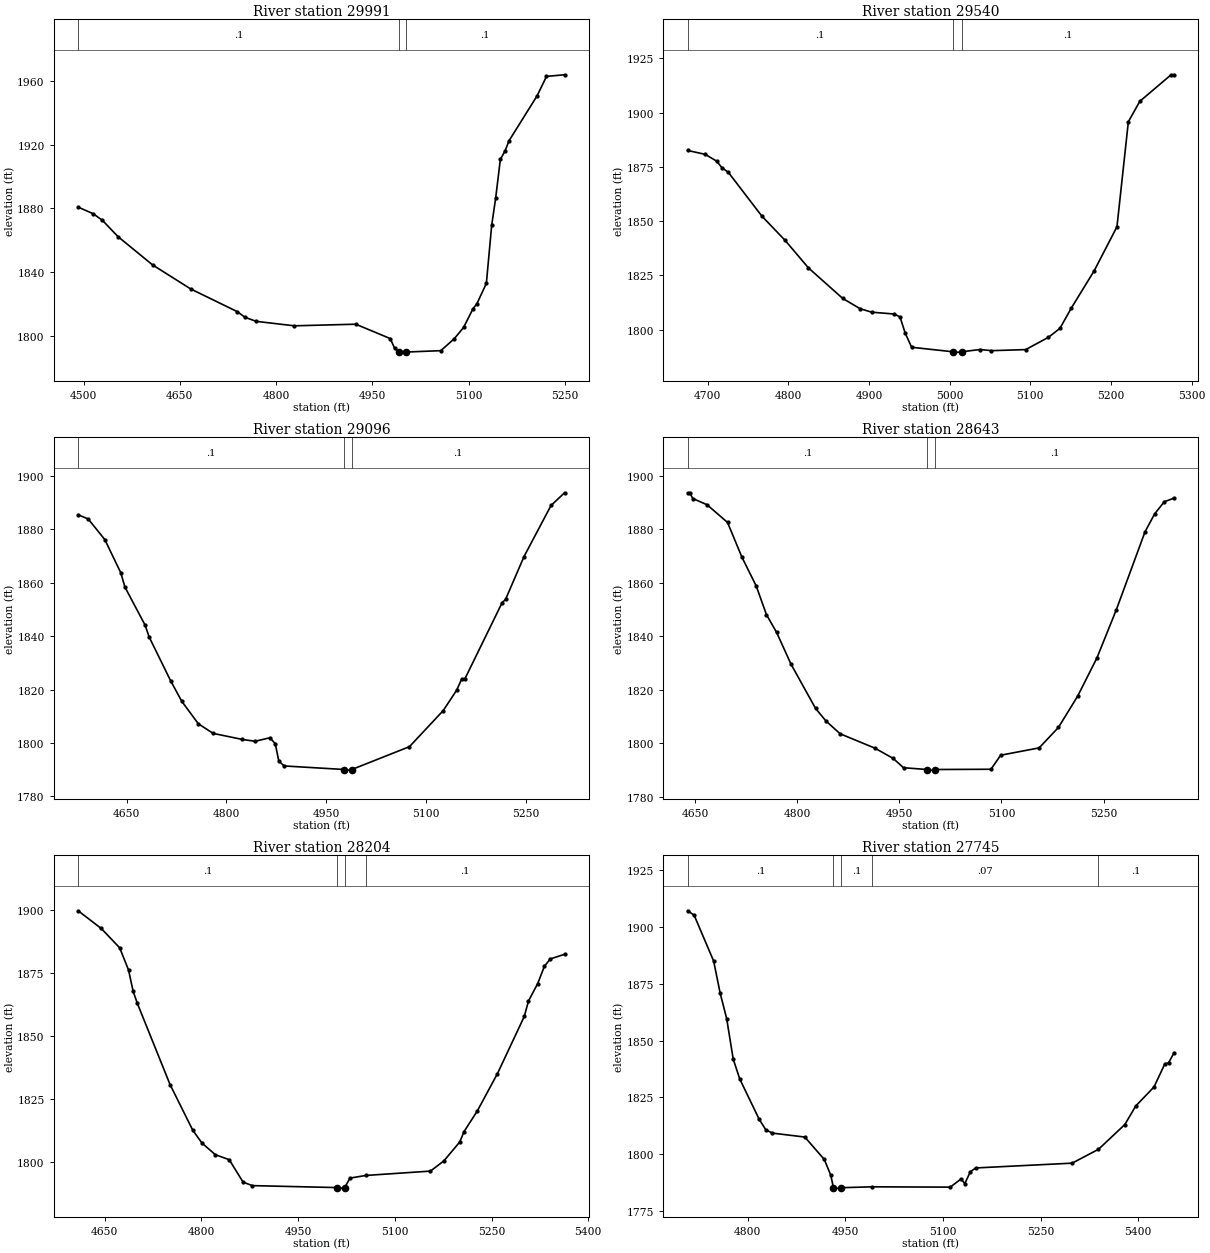
Type RM Length L Ch R = 1,29991,451,451,451
BEGIN DESCRIPTION:
Palmer Creek 57.0
END DESCRIPTION:
XS GIS Cut Line= 3
      1907136.54     13871246.57      1907325.00     13870775.00
      1907474.98     13870575.03
#Sta/Elev= 30
  4491.6 1880.72  4514.8 1876.64  4529.4 1872.43  4553.7 1862.18  4607.5 1844.43
  4666.8 1829.33  4739.5 1815.04  4751.7 1811.45  4769.1 1808.93  4828.4 1806.13
  4924.1 1807.14  4977.9 1798.10  4984.6 1792.05  4991.1 1789.64  4991.6 1789.14
  5002.4 1789.64  5056.7 1790.51  5077.6 1798.03  5092.1 1805.08  5106.7 1816.79
  5113.0 1820.11  5127.6 1832.82  5135.9 1869.32  5142.1 1886.46  5149.4 1910.72
  5156.7 1916.08  5163.0 1922.51  5206.7 1950.75  5221.3 1962.93  5249.4 1963.94
#Mann=3,-1,0
  4491.6     0.1       0  4991.1    0.05       0  5002.4     0.1       0
Bank Sta=4991.1,5002.4
Exp/Cntr=0.3,0.1

Type RM Length L Ch R = 1,29540,444,444,444
BEGIN DESCRIPTION:
Palmer Creek 56.0
END DESCRIPTION:
XS GIS Cut Line= 3
      1907225.01     13871324.99      1907475.00     13871125.00
      1907675.01     13870924.99
#Sta/Elev= 30
  4675.1 1882.55  4696.7 1880.78  4711.1 1877.64  4717.5 1874.65  4725.5 1872.52
  4767.1 1852.35  4795.9 1841.19  4824.8 1828.53  4867.2 1814.50  4888.8 1809.73
  4903.2 1808.12  4931.2 1807.27  4938.4 1805.93  4944.8 1798.52  4952.8 1791.97
  5003.7 1789.90  5004.2 1789.40  5015.1 1789.90  5037.7 1790.93  5051.8 1790.40
  5094.2 1790.89  5122.5 1796.56  5136.7 1800.67  5150.8 1810.01  5179.1 1827.14
  5207.4 1847.44  5221.5 1895.74  5235.7 1905.17  5274.5 1917.39  5278.1 1917.39
#Mann=3,-1,0
  4675.1     0.1       0  5003.7    0.05       0  5015.1     0.1       0
Bank Sta=5003.7,5015.1
Exp/Cntr=0.3,0.1

Type RM Length L Ch R = 1,29096,453,453,453
BEGIN DESCRIPTION:
Palmer Creek 55.0
END DESCRIPTION:
XS GIS Cut Line= 3
      1907374.98     13871575.01      1907775.00     13871425.00
      1908075.04     13871374.99
#Sta/Elev= 30
  4577.1 1885.44  4592.3 1883.83  4617.2 1876.12  4641.2 1863.71  4647.4 1858.38
  4677.7 1844.14  4683.9 1839.66  4716.0 1823.37  4732.9 1815.62  4757.8 1807.22
  4780.0 1803.62  4823.7 1801.36  4843.2 1800.66  4865.5 1801.99  4873.5 1799.74
  4878.8 1793.26  4886.8 1791.43  4977.3 1790.10  4977.8 1789.60  4988.7 1790.10
  5075.3 1798.65  5126.0 1812.13  5146.3 1819.78  5153.9 1824.00  5158.9 1824.15
  5214.7 1852.56  5219.8 1853.75  5247.6 1869.81  5288.2 1888.91  5308.5 1893.66
#Mann=3,-1,0
  4577.1     0.1       0  4977.3    0.05       0  4988.7     0.1       0
Bank Sta=4977.3,4988.7
Exp/Cntr=0.3,0.1

Type RM Length L Ch R = 1,28643,439,439,439
BEGIN DESCRIPTION:
Palmer Creek 54.0
END DESCRIPTION:
XS GIS Cut Line= 3
      1907774.97     13872075.04      1907975.00     13871775.00
      1908225.03     13871524.97
#Sta/Elev= 30
  4639.2 1893.65  4642.3 1893.65  4646.8 1891.51  4667.8 1889.16  4697.8 1882.57
  4718.9 1869.60  4739.9 1858.83  4754.9 1848.14  4769.9 1841.44  4791.0 1829.61
  4827.0 1813.09  4842.1 1808.43  4863.1 1803.59  4914.2 1798.22  4941.2 1794.36
  4956.2 1790.90  4990.8 1790.24  4991.3 1789.74  5002.7 1790.24  5084.7 1790.33
  5098.8 1795.57  5155.4 1798.32  5183.7 1805.96  5211.9 1817.64  5240.2 1831.91
  5268.5 1849.79  5310.9 1879.10  5325.1 1885.81  5339.2 1890.30  5353.4 1891.65
#Mann=3,-1,0
  4639.2     0.1       0  4990.8    0.05       0  5002.7     0.1       0
Bank Sta=4990.8,5002.7
Exp/Cntr=0.3,0.1

Type RM Length L Ch R = 1,28204,459,459,459
BEGIN DESCRIPTION:
Palmer Creek 53.0
END DESCRIPTION:
XS GIS Cut Line= 3
      1908025.00     13872275.00      1908275.00     13871975.00
      1908374.99     13871625.02
#Sta/Elev= 30
  4608.7 1899.88  4644.5 1892.83  4673.1 1885.14  4686.8 1876.33  4694.0 1867.81
  4700.5 1863.02  4751.2 1830.74  4786.4 1812.58  4800.7 1807.45  4821.5 1802.81
  4843.0 1800.82  4864.5 1791.90  4878.8 1790.50  5010.2 1789.72  5010.7 1789.22
  5022.1 1789.72  5030.4 1793.49  5055.1 1794.55  5155.2 1796.28  5176.0 1800.33
  5200.7 1807.88  5207.2 1811.95  5228.0 1820.26  5259.2 1835.11  5300.8 1857.85
  5307.3 1863.98  5321.6 1870.93  5332.0 1877.80  5341.1 1880.71  5363.2 1882.56
#Mann=4,-1,0
  4608.7     0.1       0  5010.2    0.05       0  5022.1     0.1       0
  5055.1     0.1       0
Bank Sta=5010.2,5022.1
Exp/Cntr=0.3,0.1

Type RM Length L Ch R = 1,27745,412,412,412
BEGIN DESCRIPTION:
Palmer Creek 52.0
END DESCRIPTION:
XS GIS Cut Line= 3
      1908625.00     13872425.00      1908625.00     13872125.00
      1908425.00     13871725.01
#Sta/Elev= 30
  4707.8 1907.15  4717.8 1905.21  4747.8 1884.98  4757.8 1870.83  4767.8 1859.66
  4777.8 1841.87  4787.8 1833.11  4817.8 1815.27  4827.8 1810.76  4837.8 1809.24
  4887.8 1807.50  4917.8 1797.62  4927.8 1790.60  4931.8 1785.19  4932.3 1784.69
  4943.8 1785.19  4991.2 1785.58  5111.2 1785.44  5128.0 1789.06  5133.6 1786.97
  5142.0 1792.15  5150.3 1793.89  5298.5 1796.00  5339.0 1802.10  5379.5 1813.02
  5396.3 1821.20  5424.3 1829.56  5441.0 1839.77  5446.6 1840.16  5455.0 1844.55
#Mann=5,-1,0
  4707.8     0.1       0  4931.8    0.05       0  4943.8     0.1       0
  4991.2    0.07       0  5339.0     0.1       0
Bank Sta=4931.8,4943.8
Exp/Cntr=0.3,0.1

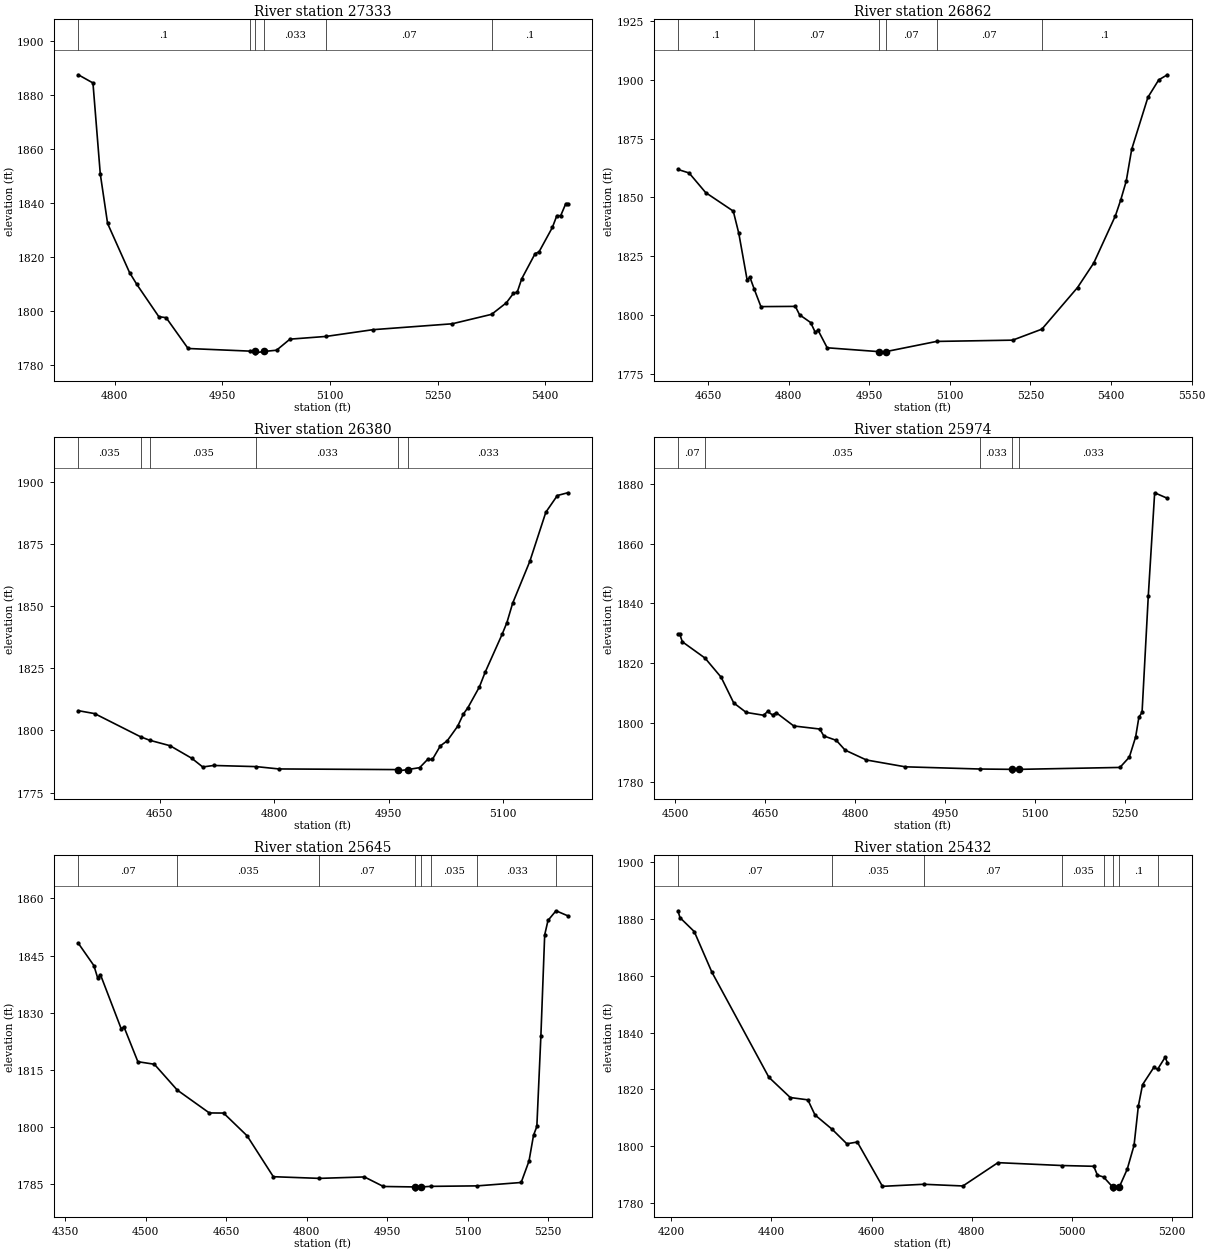
Type RM Length L Ch R = 1,27333,471,471,471
BEGIN DESCRIPTION:
Palmer Creek 51.0
END DESCRIPTION:
XS GIS Cut Line= 3
      1909025.00     13872374.99      1908975.00     13872125.00
      1908825.02     13871725.04
#Sta/Elev= 30
  4749.2 1887.67  4769.6 1884.64  4779.8 1850.96  4790.0 1832.58  4820.6 1814.40
  4830.8 1809.98  4861.4 1798.05  4871.6 1797.68  4902.2 1786.26  4988.9 1785.28
  4995.5 1785.15  4996.0 1784.65  5007.6 1785.15  5025.5 1785.62  5044.2 1789.72
  5094.5 1790.73  5159.9 1793.23  5270.3 1795.41  5325.3 1798.92  5345.9 1803.20
  5355.7 1806.69  5361.0 1807.15  5367.3 1812.11  5386.0 1821.44  5391.3 1822.02
  5410.0 1831.12  5416.2 1835.47  5421.6 1835.48  5428.7 1839.94  5431.3 1839.94
#Mann=6,-1,0
  4749.2     0.1       0  4988.9   0.033       0  4995.5   0.033       0
  5007.6   0.033       0  5094.5    0.07       0  5325.3     0.1       0
Bank Sta=4995.5,5007.6
Exp/Cntr=0.3,0.1

Type RM Length L Ch R = 1,26862,482,482,482
BEGIN DESCRIPTION:
Palmer Creek 50.0
END DESCRIPTION:
XS GIS Cut Line= 3
      1909280.38     13872425.15      1909375.00     13872025.00
      1909317.41     13871529.11
#Sta/Elev= 30
  4594.3 1861.90  4615.0 1860.41  4645.8 1852.08  4697.2 1844.20  4707.5 1834.73
  4723.0 1814.93  4728.1 1816.15  4736.3 1810.98  4748.6 1803.63  4812.7 1803.73
  4820.5 1800.16  4841.1 1796.87  4849.8 1792.66  4854.9 1793.61  4871.9 1786.14
  4968.6 1784.49  4969.1 1783.99  4980.7 1784.49  5075.4 1788.84  5216.9 1789.38
  5271.3 1794.05  5337.7 1811.75  5367.9 1822.18  5408.2 1842.27  5418.2 1849.07
  5428.3 1856.99  5438.4 1870.45  5468.6 1892.56  5488.7 1899.95  5504.7 1902.13
#Mann=6,-1,0
  4594.3     0.1       0  4736.3    0.07       0  4968.6   0.033       0
  4980.7    0.07       0  5075.4    0.07       0  5271.3     0.1       0
Bank Sta=4968.6,4980.7
Exp/Cntr=0.3,0.1

Type RM Length L Ch R = 1,26380,406,406,406
BEGIN DESCRIPTION:
Palmer Creek 49.0
END DESCRIPTION:
XS GIS Cut Line= 3
      1909474.98     13872225.01      1909825.00     13871925.00
      1909925.01     13871774.98
#Sta/Elev= 30
  4543.2 1807.94  4564.6 1806.76  4624.8 1797.43  4636.6 1796.05  4663.4 1793.84
  4691.9 1788.78  4706.2 1785.29  4720.5 1785.89  4776.3 1785.43  4806.1 1784.49
  4962.4 1784.23  4962.9 1783.73  4974.6 1784.23  4990.5 1785.01  5000.9 1788.30
  5007.2 1788.30  5017.7 1793.80  5026.7 1795.82  5040.3 1801.66  5047.8 1806.57
  5053.8 1809.17  5068.8 1817.48  5076.3 1823.36  5098.8 1838.81  5104.9 1843.42
  5112.4 1851.18  5134.9 1868.03  5155.9 1887.80  5171.0 1894.52  5184.5 1895.62
#Mann=6,-1,0
  4543.2   0.035       0  4624.8    0.07       0  4636.6   0.035       0
  4776.3   0.033       0  4962.4   0.033       0  4974.6   0.033       0
Bank Sta=4962.4,4974.6
Exp/Cntr=0.3,0.1

Type RM Length L Ch R = 1,25974,329,329,329
BEGIN DESCRIPTION:
Palmer Creek 48.0
END DESCRIPTION:
XS GIS Cut Line= 3
      1909575.01     13872574.99      1909983.23     13872272.64
      1910275.03     13872174.99
#Sta/Elev= 30
  4504.9 1829.56  4508.0 1829.56  4512.2 1827.10  4550.0 1821.63  4576.9 1815.20
  4597.8 1806.60  4618.6 1803.41  4647.8 1802.45  4654.2 1803.74  4662.5 1802.56
  4668.7 1803.32  4697.9 1798.87  4741.3 1797.84  4748.0 1795.52  4768.9 1794.03
  4783.5 1790.77  4819.0 1787.46  4883.7 1785.17  5008.3 1784.43  5061.4 1784.32
  5061.9 1783.82  5073.6 1784.32  5241.6 1784.96  5257.3 1788.42  5267.8 1795.19
  5273.2 1801.78  5278.5 1803.44  5288.9 1842.55  5299.5 1877.07  5320.6 1875.23
#Mann=5,-1,0
  4504.9    0.07       0  4550.0   0.035       0  5008.3   0.033       0
  5061.4   0.035       0  5073.6   0.033       0
Bank Sta=5061.4,5073.6
Exp/Cntr=0.3,0.1

Type RM Length L Ch R = 1,25645,213,213,213
BEGIN DESCRIPTION:
Palmer Creek 47.0
END DESCRIPTION:
XS GIS Cut Line= 3
      1909506.72     13872628.16      1909993.48     13872521.36
      1910325.02     13872274.99
#Sta/Elev= 30
  4374.7 1848.23  4403.7 1842.36  4410.8 1839.09  4415.9 1839.98  4454.6 1825.74
  4459.7 1826.26  4485.6 1817.10  4516.3 1816.43  4559.0 1809.64  4618.7 1803.63
  4645.2 1803.60  4689.0 1797.63  4737.9 1786.87  4823.8 1786.43  4907.5 1786.81
  4942.9 1784.30  5001.5 1784.18  5002.0 1783.68  5013.7 1784.18  5030.7 1784.33
  5117.8 1784.46  5199.5 1785.35  5214.1 1790.99  5222.5 1797.75  5228.7 1800.09
  5236.2 1823.81  5243.3 1850.43  5249.5 1854.24  5264.4 1856.77  5286.1 1855.46
#Mann=8,-1,0
  4374.7    0.07       0  4559.0   0.035       0  4823.8    0.07       0
  5001.5    0.05       0  5013.7    0.07       0  5030.7   0.035       0
  5117.8   0.033       0  5264.4     0.1       0
Bank Sta=5001.5,5013.7
Exp/Cntr=0.3,0.1

Type RM Length L Ch R = 1,25432,122,122,122
BEGIN DESCRIPTION:
Palmer Creek D1
END DESCRIPTION:
XS GIS Cut Line= 5
      1909586.53     13872862.23      1909905.96     13872580.99
      1910149.01     13872521.97      1910291.37     13872504.61
      1910360.41     13872363.07
#Sta/Elev= 30
  4213.6 1882.91  4217.6 1880.49  4246.1 1875.58  4281.2 1861.30  4395.0 1824.22
  4437.7 1817.08  4472.8 1816.26  4487.0 1810.95  4521.3 1805.88  4550.6 1800.77
  4571.5 1801.39  4621.7 1785.77  4704.0 1786.50  4782.3 1785.90  4852.2 1794.12
  4979.8 1793.11  5043.4 1792.84  5050.7 1789.72  5063.0 1789.06  5081.8 1785.39
  5082.3 1784.89  5094.0 1785.39  5110.2 1791.82  5123.8 1800.22  5132.4 1814.06
  5140.8 1821.62  5163.3 1827.70  5170.8 1827.02  5185.9 1831.29  5190.2 1829.38
#Mann=8,-1,0
  4213.6    0.07       0  4521.3   0.035       0  4704.0    0.07       0
  4979.8   0.035       0  5063.0     0.1       0  5081.8   0.035       0
  5094.0     0.1       0  5170.8     0.1       0
Bank Sta=5081.8,5094
Exp/Cntr=0.3,0.1