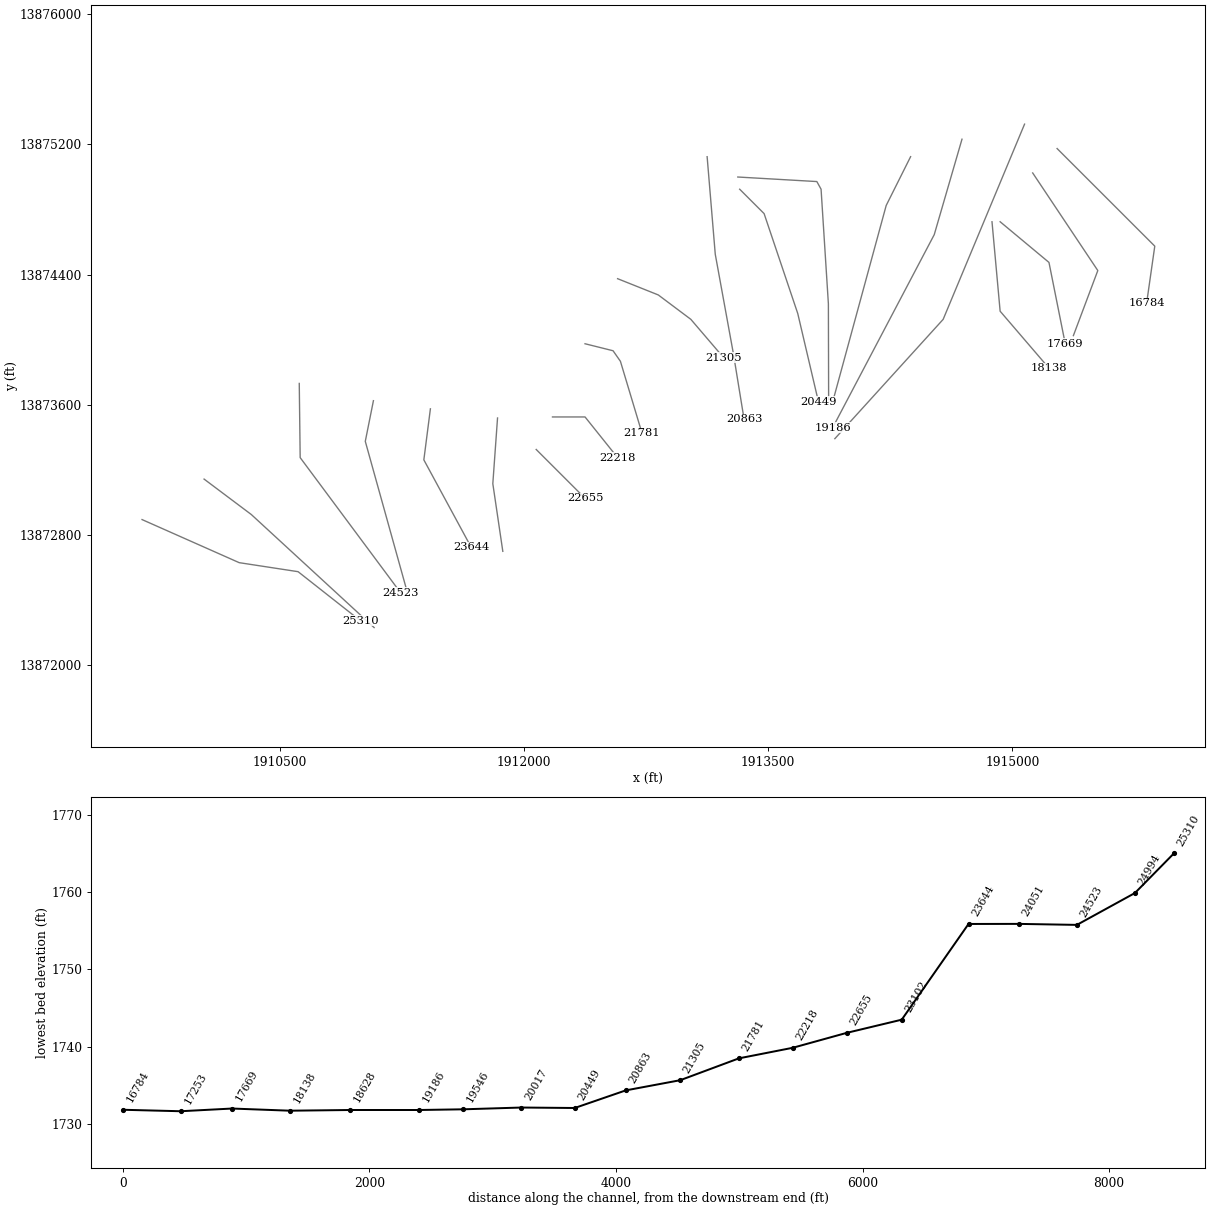
HEC-RAS study Palmer Creek.prj: Palmer Creek Base Level Engineering

--- Palmer Creek.g01 (geometry) --- (continued)

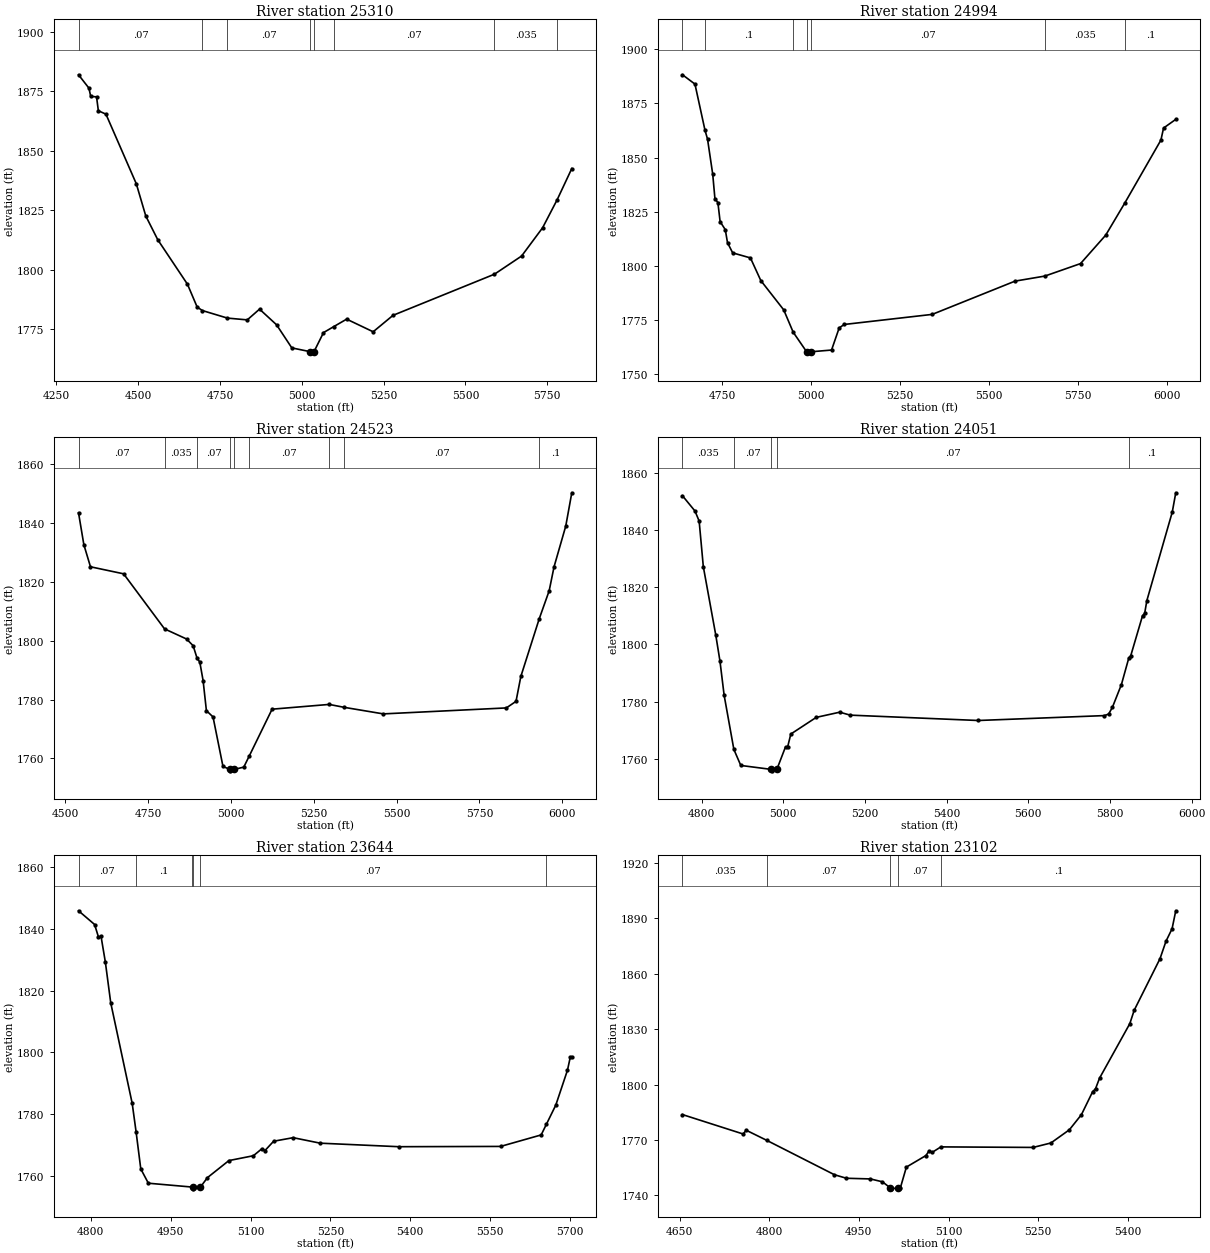
Type RM Length L Ch R = 1,25310,316,316,316
BEGIN DESCRIPTION:
Palmer Creek 46.1
END DESCRIPTION:
XS GIS Cut Line= 4
      1909653.63     13872894.12      1910250.38     13872629.24
      1910612.12     13872573.82      1910995.87     13872271.47
#Sta/Elev= 30
  4317.6 1881.87  4349.4 1876.26  4354.9 1872.77  4372.7 1872.60  4378.2 1866.76
  4401.4 1865.32  4494.2 1836.06  4523.2 1822.52  4559.8 1812.54  4650.5 1793.86
  4680.1 1784.27  4696.1 1782.79  4772.6 1779.62  4833.3 1778.87  4870.8 1783.38
  4922.8 1776.81  4969.4 1767.10  5025.1 1765.52  5025.6 1765.02  5037.3 1765.52
  5066.2 1773.52  5097.2 1776.01  5137.0 1779.18  5218.0 1773.87  5278.7 1780.78
  5588.7 1798.07  5671.6 1805.70  5735.8 1817.58  5780.5 1829.42  5825.0 1842.47
#Mann=8,-1,0
  4317.6    0.07       0  4696.1   0.035       0  4772.6    0.07       0
  5025.1    0.05       0  5037.3    0.07       0  5097.2    0.07       0
  5588.7   0.035       0  5780.5     0.1       0
Bank Sta=5025.1,5037.3
Exp/Cntr=0.3,0.1

Type RM Length L Ch R = 1,24994,471,471,471
BEGIN DESCRIPTION:
Palmer Creek 46.0
END DESCRIPTION:
XS GIS Cut Line= 3
      1910034.61     13873143.06      1910325.00     13872925.00
      1911079.26     13872230.29
#Sta/Elev= 30
  4637.4 1888.18  4672.5 1883.88  4700.6 1862.69  4707.9 1858.49  4722.5 1842.31
  4728.7 1831.04  4737.1 1829.17  4743.3 1820.44  4757.9 1816.71  4764.1 1810.71
  4778.7 1806.01  4828.7 1803.68  4857.9 1793.23  4922.4 1779.71  4949.0 1769.42
  4986.8 1760.39  4987.3 1759.89  4999.8 1760.39  5057.0 1761.18  5078.5 1771.40
  5092.7 1772.98  5340.4 1777.63  5573.6 1792.98  5657.5 1795.31  5757.9 1801.07
  5828.8 1814.19  5882.7 1829.07  5984.2 1858.05  5991.6 1863.60  6026.0 1867.61
#Mann=7,-1,0
  4637.4    0.07       0  4700.6     0.1       0  4949.0    0.07       0
  4986.8    0.05       0  4999.8    0.07       0  5657.5   0.035       0
  5882.7     0.1       0
Bank Sta=4986.8,4999.8
Exp/Cntr=0.3,0.1

Type RM Length L Ch R = 1,24523,472,472,472
BEGIN DESCRIPTION:
Palmer Creek 45.0
END DESCRIPTION:
XS GIS Cut Line= 3
      1910619.40     13873731.06      1910625.00     13873275.00
      1911241.05     13872445.66
#Sta/Elev= 30
  4539.8 1843.50  4555.9 1832.65  4575.9 1825.13  4675.9 1822.74  4799.5 1804.02
  4865.9 1800.58  4885.9 1798.29  4897.9 1793.97  4905.9 1792.78  4915.9 1786.45
  4925.9 1776.21  4945.9 1774.09  4975.9 1757.26  4996.5 1756.26  4997.0 1755.76
  5009.9 1756.26  5038.7 1757.02  5055.1 1760.77  5124.2 1776.72  5296.7 1778.34
  5341.7 1777.35  5460.0 1775.12  5831.4 1777.15  5860.6 1779.38  5875.2 1787.86
  5930.5 1807.39  5960.7 1816.97  5975.4 1825.11  6010.8 1838.98  6029.0 1850.29
#Mann=9,-1,0
  4539.8    0.07       0  4799.5   0.035       0  4897.9    0.07       0
  4996.5    0.05       0  5009.9    0.07       0  5055.1    0.07       0
  5296.7   0.035       0  5341.7    0.07       0  5930.5     0.1       0
Bank Sta=4996.5,5009.9
Exp/Cntr=0.3,0.1

Type RM Length L Ch R = 1,24051,407,407,407
BEGIN DESCRIPTION:
Palmer Creek 44.0
END DESCRIPTION:
XS GIS Cut Line= 3
      1911075.00     13873625.01      1911025.00     13873375.00
      1911280.49     13872456.75
#Sta/Elev= 30
  4753.0 1851.88  4783.6 1846.56  4793.8 1843.06  4804.0 1827.15  4834.6 1803.20
  4844.8 1794.16  4855.0 1782.26  4878.8 1763.37  4895.8 1757.77  4970.6 1756.39
  4971.1 1755.89  4984.1 1756.39  5005.4 1764.29  5010.6 1764.29  5018.3 1768.73
  5080.6 1774.55  5138.1 1776.36  5163.7 1775.33  5477.3 1773.46  5786.5 1775.17
  5796.8 1775.73  5806.0 1778.09  5828.0 1786.01  5846.1 1795.29  5850.6 1795.95
  5879.7 1810.03  5884.9 1810.82  5890.3 1815.31  5952.5 1846.18  5961.1 1852.93
#Mann=5,-1,0
  4753.0   0.035       0  4878.8    0.07       0  4970.6    0.05       0
  4984.1    0.07       0  5846.1     0.1       0
Bank Sta=4970.6,4984.1
Exp/Cntr=0.3,0.1

Type RM Length L Ch R = 1,23644,542,542,542
BEGIN DESCRIPTION:
Palmer Creek 43.0
END DESCRIPTION:
XS GIS Cut Line= 3
      1911425.00     13873575.00      1911384.74     13873261.21
      1911675.00     13872724.99
#Sta/Elev= 30
  4777.1 1845.83  4807.3 1841.39  4814.4 1837.42  4819.4 1837.55  4827.5 1829.22
  4837.6 1816.03  4877.9 1783.51  4885.2 1774.31  4894.0 1762.33  4908.2 1757.70
  4990.7 1756.45  4992.2 1756.38  4992.7 1755.88  5005.7 1756.38  5019.1 1759.50
  5059.4 1765.02  5105.4 1766.59  5121.5 1768.87  5127.2 1768.27  5143.4 1771.28
  5180.1 1772.43  5230.9 1770.65  5378.4 1769.51  5569.5 1769.60  5645.7 1773.32
  5655.6 1776.80  5673.2 1782.98  5695.1 1794.27  5700.3 1798.44  5703.2 1798.44
#Mann=6,-1,0
  4777.1    0.07       0  4885.2     0.1       0  4990.7    0.07       0
  4992.2    0.05       0  5005.7    0.07       0  5655.6     0.1       0
Bank Sta=4992.2,5005.7
Exp/Cntr=0.3,0.1

Type RM Length L Ch R = 1,23102,447,447,447
BEGIN DESCRIPTION:
Palmer Creek 42.0
END DESCRIPTION:
XS GIS Cut Line= 3
      1911837.45     13873518.64      1911808.46     13873114.77
      1911869.83     13872698.89
#Sta/Elev= 30
  4654.9 1783.71  4756.4 1773.19  4761.4 1775.25  4795.6 1769.80  4909.2 1751.11
  4929.2 1749.21  4969.3 1748.85  4989.4 1747.29  5002.7 1743.98  5003.2 1743.48
  5016.2 1743.98  5019.5 1744.10  5029.5 1755.27  5062.2 1761.52  5067.5 1764.06
  5072.5 1763.20  5087.2 1766.21  5241.5 1765.92  5271.3 1768.33  5302.2 1775.48
  5322.4 1783.69  5341.0 1796.04  5346.0 1797.77  5352.7 1803.47  5403.3 1832.97
  5410.6 1840.21  5453.8 1868.16  5463.9 1877.69  5474.0 1884.38  5480.2 1894.14
#Mann=5,-1,0
  4654.9   0.035       0  4795.6    0.07       0  5002.7    0.05       0
  5016.2    0.07       0  5087.2     0.1       0
Bank Sta=5002.7,5016.2
Exp/Cntr=0.3,0.1

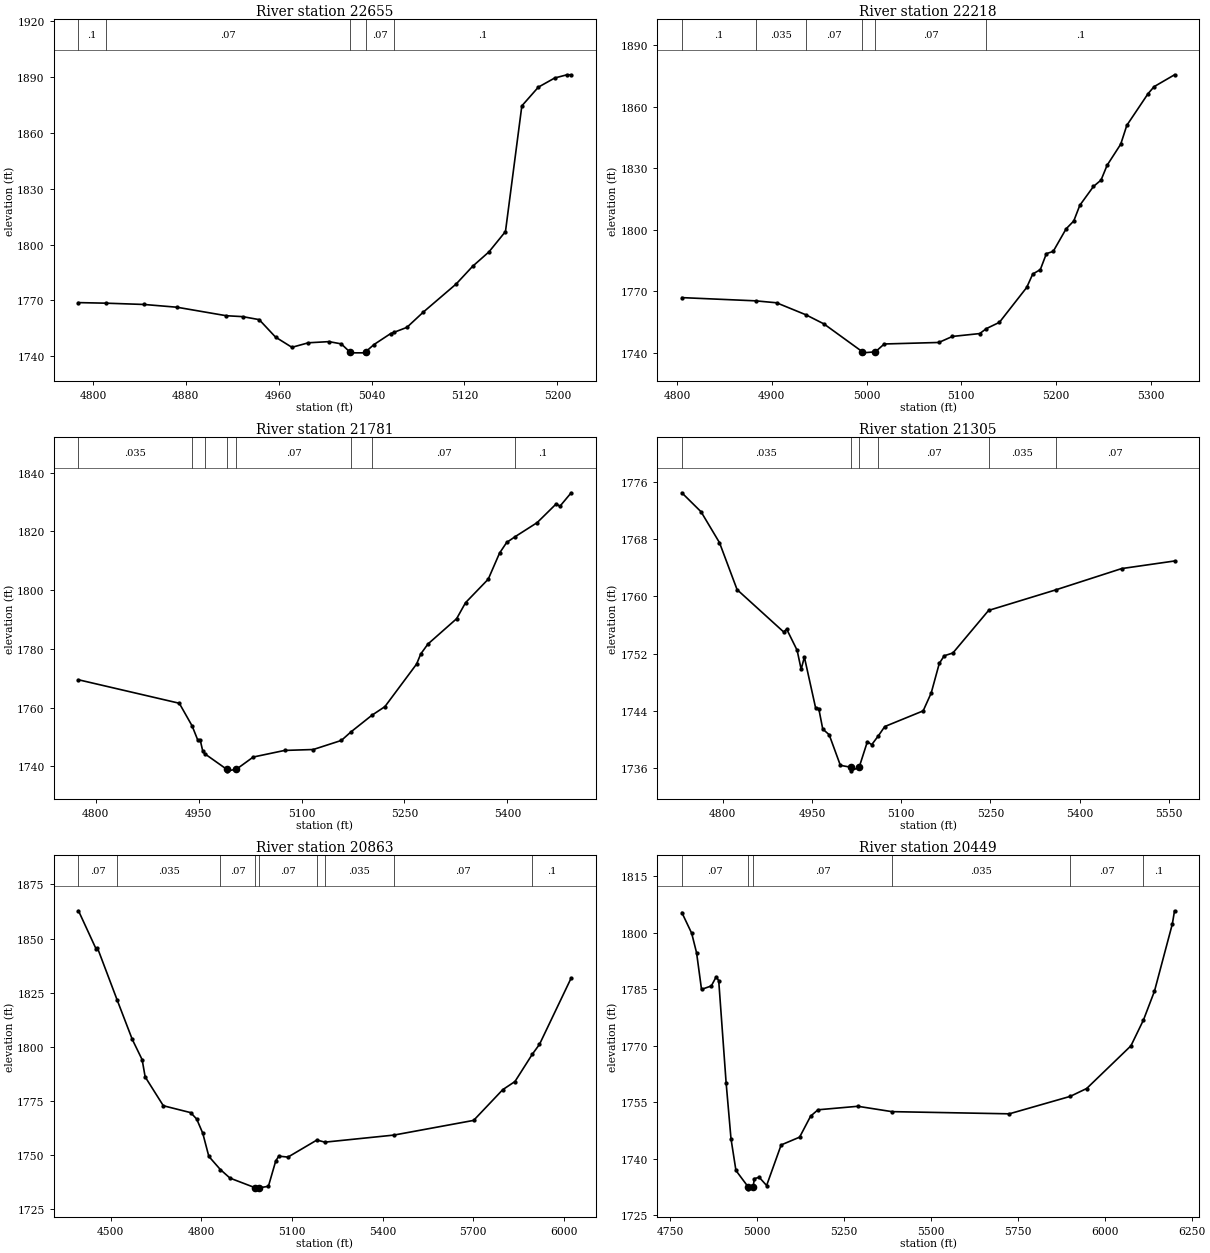
Type RM Length L Ch R = 1,22655,437,437,437
BEGIN DESCRIPTION:
Palmer Creek 41.0
END DESCRIPTION:
XS GIS Cut Line= 3
      1912075.01     13873324.99      1912225.00     13873175.00
      1912375.03     13873024.97
#Sta/Elev= 30
  4787.6 1768.78  4811.2 1768.48  4844.2 1767.78  4872.4 1766.30  4914.9 1761.73
  4929.0 1761.24  4943.2 1759.63  4957.3 1750.23  4971.4 1744.74  4985.6 1747.18
  5003.3 1747.80  5013.9 1746.59  5021.2 1742.27  5021.7 1741.77  5034.3 1741.77
  5034.8 1742.27  5042.1 1746.24  5056.3 1752.08  5059.1 1752.75  5070.4 1755.46
  5084.6 1763.71  5112.9 1778.83  5127.0 1788.30  5141.1 1796.08  5155.3 1807.00
  5169.4 1874.58  5183.6 1884.65  5197.7 1889.58  5208.3 1891.31  5211.9 1891.31
#Mann=5,-1,0
  4787.6     0.1       0  4811.2    0.07       0  5021.2    0.05       0
  5034.8    0.07       0  5059.1     0.1       0
Bank Sta=5021.2,5034.8
Exp/Cntr=0.3,0.1

Type RM Length L Ch R = 1,22218,437,437,437
BEGIN DESCRIPTION:
Palmer Creek 40.0
END DESCRIPTION:
XS GIS Cut Line= 3
      1912174.95     13873525.00      1912375.00     13873525.00
      1912575.00     13873275.00
#Sta/Elev= 30
  4805.0 1766.78  4882.8 1765.21  4905.0 1764.26  4935.9 1758.42  4955.0 1753.96
  4995.7 1740.34  4996.2 1739.84  5009.4 1740.34  5018.7 1744.16  5076.3 1744.90
  5090.7 1747.84  5119.5 1749.24  5126.6 1751.68  5140.3 1754.72  5169.1 1771.73
  5175.5 1778.29  5183.5 1780.45  5189.9 1788.24  5197.1 1789.32  5210.7 1800.32
  5218.8 1804.17  5225.2 1811.83  5239.6 1821.01  5247.6 1824.12  5254.0 1831.34
  5268.4 1841.65  5274.8 1850.81  5297.2 1866.25  5303.6 1869.69  5325.2 1875.49
#Mann=6,-1,0
  4805.0     0.1       0  4882.8   0.035       0  4935.9    0.07       0
  4995.7    0.05       0  5009.4    0.07       0  5126.6     0.1       0
Bank Sta=4995.7,5009.4
Exp/Cntr=0.3,0.1

Type RM Length L Ch R = 1,21781,476,476,476
BEGIN DESCRIPTION:
Palmer Creek 39.0
END DESCRIPTION:
XS GIS Cut Line= 4
      1912374.97     13873975.01      1912547.07     13873931.98
      1912592.36     13873867.14      1912725.00     13873425.00
#Sta/Elev= 30
  4774.9 1769.47  4921.8 1761.48  4940.5 1753.77  4948.7 1748.97  4952.3 1748.97
  4956.1 1745.10  4959.2 1744.24  4991.1 1738.97  4991.6 1738.47  5004.8 1738.97
  5029.6 1743.17  5075.4 1745.42  5117.1 1745.73  5158.0 1748.82  5172.3 1751.78
  5202.6 1757.40  5221.5 1760.33  5267.7 1774.83  5273.7 1778.25  5284.2 1781.64
  5326.0 1790.26  5339.0 1795.71  5372.1 1803.72  5388.6 1812.60  5399.0 1816.23
  5411.4 1818.20  5443.4 1822.97  5471.2 1829.36  5476.5 1828.52  5493.0 1833.13
#Mann=8,-1,0
  4774.9   0.035       0  4940.5     0.1       0  4959.2    0.07       0
  4991.1    0.05       0  5004.8    0.07       0  5172.3     0.1       0
  5202.6    0.07       0  5411.4     0.1       0
Bank Sta=4991.1,5004.8
Exp/Cntr=0.3,0.1

Type RM Length L Ch R = 1,21305,442,442,442
BEGIN DESCRIPTION:
Palmer Creek 38.0
END DESCRIPTION:
XS GIS Cut Line= 4
      1912575.02     13874374.99      1912825.00     13874275.00
      1913025.00     13874125.00      1913225.79     13873890.04
#Sta/Elev= 30
  4731.2 1774.45  4763.5 1771.80  4794.5 1767.49  4824.1 1760.93  4902.2 1755.04
  4907.5 1755.41  4925.0 1752.47  4931.8 1749.81  4937.2 1751.52  4956.0 1744.46
  4961.4 1744.33  4968.1 1741.47  4978.9 1740.68  4997.7 1736.41  5015.3 1736.14
  5015.8 1735.64  5029.3 1736.14  5043.1 1739.71  5050.4 1739.29  5061.7 1740.54
  5072.3 1741.82  5136.9 1744.01  5150.4 1746.50  5164.0 1750.63  5172.3 1751.70
  5186.9 1752.09  5246.9 1758.03  5359.5 1760.89  5470.6 1763.87  5559.5 1764.93
#Mann=6,-1,0
  4731.2   0.035       0  5015.3   0.035       0  5029.3   0.035       0
  5061.7    0.07       0  5246.9   0.035       0  5359.5    0.07       0
Bank Sta=5015.3,5029.3
Exp/Cntr=0.3,0.1

Type RM Length L Ch R = 1,20863,414,414,414
BEGIN DESCRIPTION:
Palmer Creek 37.0
END DESCRIPTION:
XS GIS Cut Line= 4
      1913125.00     13875124.97      1913175.00     13874525.00
      1913286.33     13873914.19      1913351.94     13873511.32
#Sta/Elev= 30
  4393.2 1862.82  4450.9 1845.35  4455.9 1845.70  4520.9 1821.70  4571.3 1803.37
  4603.9 1794.02  4613.9 1786.06  4674.1 1772.72  4764.5 1769.54  4784.5 1766.58
  4804.6 1760.02  4824.7 1749.32  4862.8 1743.24  4894.9 1739.27  4978.2 1734.82
  4978.7 1734.32  4992.3 1734.82  5021.9 1735.49  5046.1 1747.16  5056.2 1749.43
  5086.7 1748.99  5182.5 1756.88  5208.8 1755.89  5437.4 1759.16  5701.3 1765.95
  5797.7 1780.15  5838.2 1783.92  5895.4 1796.49  5919.3 1801.08  6024.3 1831.77
#Mann=9,-1,0
  4393.2    0.07       0  4520.9   0.035       0  4862.8    0.07       0
  4978.2    0.05       0  4992.3    0.07       0  5182.5    0.07       0
  5208.8   0.035       0  5437.4    0.07       0  5895.4     0.1       0
Bank Sta=4978.2,4992.3
Exp/Cntr=0.3,0.1

Type RM Length L Ch R = 1,20449,432,432,432
BEGIN DESCRIPTION:
Palmer Creek 36.0
END DESCRIPTION:
XS GIS Cut Line= 4
      1913325.00     13874925.00      1913475.00     13874775.00
      1913681.68     13874161.01      1913808.81     13873618.78
#Sta/Elev= 30
  4783.7 1805.38  4812.0 1799.88  4826.1 1794.68  4840.3 1784.98  4868.5 1785.89
  4882.7 1788.35  4889.8 1787.26  4911.0 1760.24  4925.1 1745.32  4939.3 1736.91
  4974.6 1732.54  4975.1 1732.04  4988.7 1732.54  4992.3 1734.76  5006.3 1735.10
  5027.5 1732.92  5069.3 1743.69  5122.4 1745.76  5154.1 1751.34  5175.2 1753.02
  5289.8 1753.95  5387.8 1752.53  5725.4 1751.95  5900.6 1756.58  5947.9 1758.67
  6075.2 1770.00  6111.3 1776.87  6142.9 1784.51  6194.2 1802.31  6200.6 1805.84
#Mann=6,-1,0
  4783.7    0.07       0  4974.6    0.05       0  4988.7    0.07       0
  5387.8   0.035       0  5900.6    0.07       0  6111.3     0.1       0
Bank Sta=4974.6,4988.7
Exp/Cntr=0.3,0.1

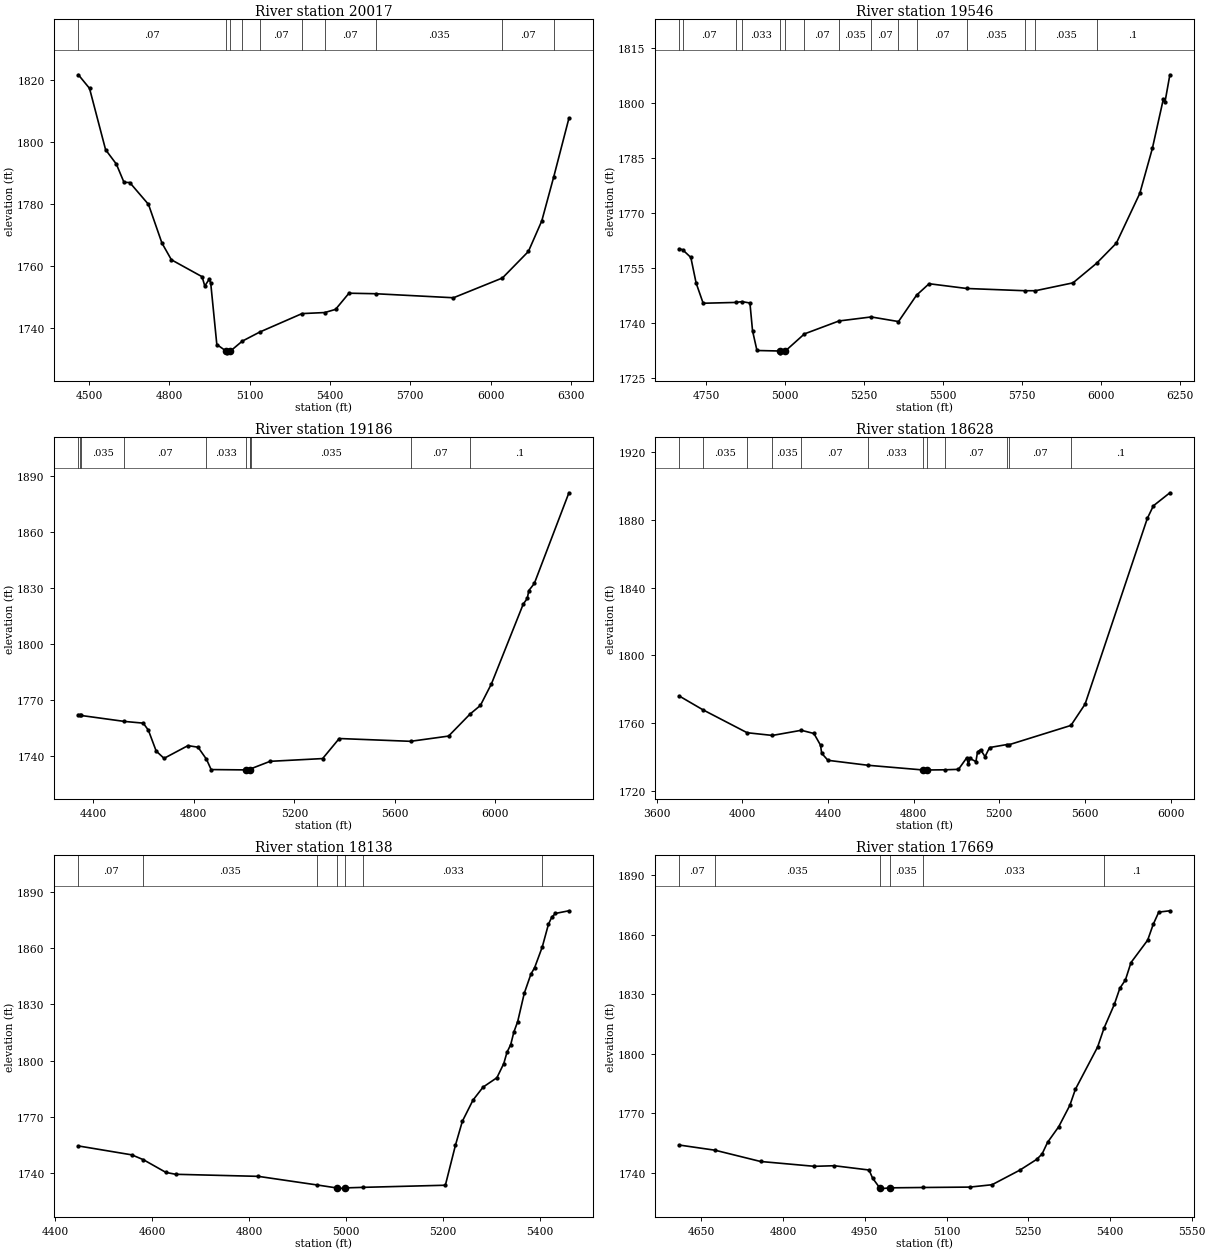
Type RM Length L Ch R = 1,20017,471,471,471
BEGIN DESCRIPTION:
Palmer Creek 35.0
END DESCRIPTION:
XS GIS Cut Line= 5
      1913313.45     13875000.00      1913799.03     13874972.06
      1913825.00     13874925.00      1913869.91     13874220.45
      1913871.42     13873633.56
#Sta/Elev= 30
  4459.8 1821.81  4501.4 1817.43  4561.5 1797.63  4601.6 1793.01  4630.3 1787.10
  4651.7 1787.05  4721.8 1779.99  4771.9 1767.54  4807.4 1762.12  4922.1 1756.66
  4932.1 1753.66  4948.4 1755.82  4954.2 1754.71  4977.1 1734.79  5012.9 1732.60
  5013.4 1732.10  5027.0 1732.60  5072.0 1735.86  5137.6 1738.81  5295.5 1744.76
  5380.3 1745.10  5420.8 1746.12  5470.9 1751.34  5570.1 1751.17  5861.4 1749.87
  6044.5 1756.26  6141.4 1764.81  6191.4 1774.67  6236.4 1788.98  6292.8 1807.77
#Mann=10,-1,0
  4459.8    0.07       0  5012.9    0.05       0  5027.0    0.07       0
  5072.0     0.1       0  5137.6    0.07       0  5295.5   0.035       0
  5380.3    0.07       0  5570.1   0.035       0  6044.5    0.07       0
  6236.4     0.1       0
Bank Sta=5012.9,5027
Exp/Cntr=0.3,0.1

Type RM Length L Ch R = 1,19546,360,360,360
BEGIN DESCRIPTION:
Palmer Creek 34.0
END DESCRIPTION:
XS GIS Cut Line= 3
      1914375.02     13875125.04      1914225.00     13874825.00
      1913904.79     13873648.76
#Sta/Elev= 30
  4664.5 1760.28  4675.0 1760.01  4700.9 1757.92  4717.7 1750.93  4740.0 1745.41
  4842.6 1745.63  4863.1 1745.85  4888.2 1745.48  4896.5 1737.88  4910.5 1732.51
  4982.7 1732.37  4983.2 1731.87  5000.4 1732.37  5060.9 1737.04  5170.3 1740.57
  5272.5 1741.67  5359.0 1740.41  5416.3 1747.62  5456.0 1750.74  5575.4 1749.44
  5758.6 1748.83  5793.0 1748.83  5912.0 1750.98  5986.6 1756.31  6049.4 1761.82
  6123.7 1775.41  6163.5 1787.68  6198.1 1801.08  6203.3 1800.25  6219.0 1807.79
#Mann=15,-1,0
  4664.5     0.1       0  4675.0    0.07       0  4842.6     0.1       0
  4863.1   0.033       0  4982.7   0.033       0  5000.4   0.033       0
  5060.9    0.07       0  5170.3   0.035       0  5272.5    0.07       0
  5359.0   0.035       0  5416.3    0.07       0  5575.4   0.035       0
  5758.6    0.07       0  5793.0   0.035       0  5986.6     0.1       0
Bank Sta=4982.7,5000.4
Exp/Cntr=0.3,0.1

Type RM Length L Ch R = 1,19186,558,558,558
BEGIN DESCRIPTION:
Palmer Creek 33.0
END DESCRIPTION:
XS GIS Cut Line= 3
      1914690.64     13875232.43      1914520.16     13874645.63
      1913895.82     13873458.35
#Sta/Elev= 30
  4340.3 1761.88  4347.6 1761.57  4350.4 1761.48  4523.2 1758.28  4598.3 1757.36
  4618.8 1753.61  4650.0 1742.38  4681.3 1738.48  4776.5 1745.30  4816.6 1744.45
  4850.1 1738.01  4868.7 1732.46  5006.3 1732.28  5006.8 1731.78  5024.0 1732.28
  5024.8 1732.43  5027.5 1732.93  5103.4 1736.88  5312.5 1738.36  5378.6 1749.11
  5662.4 1747.61  5813.8 1750.42  5899.1 1762.20  5940.4 1766.84  5984.5 1778.45
  6111.0 1821.20  6127.1 1824.22  6133.1 1828.43  6155.1 1832.25  6292.8 1880.88
#Mann=11,-1,0
  4340.3   0.035       0  4347.6    0.07       0  4350.4   0.035       0
  4523.2    0.07       0  4850.1   0.033       0  5006.3   0.033       0
  5024.0   0.033       0  5024.8     0.1       0  5027.5   0.035       0
  5662.4    0.07       0  5899.1     0.1       0
Bank Sta=5006.3,5024
Exp/Cntr=0.3,0.1

Type RM Length L Ch R = 1,18628,490,490,490
BEGIN DESCRIPTION:
Palmer Creek 32.0
END DESCRIPTION:
XS GIS Cut Line= 3
      1915075.00     13875325.00      1914575.00     13874125.00
      1913909.61     13873391.42
#Sta/Elev= 30
  3706.5 1775.98  3816.5 1767.87  4023.0 1754.31  4140.9 1752.71  4275.9 1755.75
  4334.8 1753.86  4365.7 1746.95  4371.1 1742.17  4400.4 1738.00  4587.3 1735.07
  4845.9 1732.28  4846.4 1731.78  4863.8 1732.28  4948.4 1732.40  5009.9 1732.67
  5048.7 1739.54  5056.2 1735.59  5062.9 1739.19  5091.3 1737.20  5098.8 1742.94
  5112.9 1744.29  5133.9 1740.17  5155.0 1745.55  5235.5 1747.31  5247.6 1747.28
  5534.9 1758.62  5600.9 1771.19  5891.5 1880.96  5919.9 1888.44  5996.9 1896.14
#Mann=12,-1,0
  3706.5    0.07       0  3816.5   0.035       0  4023.0    0.07       0
  4140.9   0.035       0  4275.9    0.07       0  4587.3   0.033       0
  4845.9    0.05       0  4863.8   0.033       0  4948.4    0.07       0
  5235.5   0.035       0  5247.6    0.07       0  5534.9     0.1       0
Bank Sta=4845.9,4863.8
Exp/Cntr=0.3,0.1

Type RM Length L Ch R = 1,18138,469,469,469
BEGIN DESCRIPTION:
Palmer Creek 31.0
END DESCRIPTION:
XS GIS Cut Line= 3
      1914875.00     13874724.96      1914925.00     13874175.00
      1915225.00     13873825.00
#Sta/Elev= 30
  4447.5 1754.53  4557.9 1749.78  4581.9 1747.19  4628.2 1740.45  4648.3 1739.44
  4819.0 1738.34  4940.9 1733.74  4980.7 1732.19  4981.2 1731.69  4998.6 1732.19
  5035.3 1732.48  5205.5 1733.61  5226.4 1754.99  5240.6 1767.67  5262.6 1778.95
  5283.4 1785.86  5312.0 1790.87  5326.2 1798.43  5332.8 1804.43  5340.5 1808.49
  5347.1 1815.29  5354.8 1820.66  5368.5 1835.84  5382.2 1846.03  5389.9 1849.48
  5405.7 1860.51  5418.4 1872.56  5425.0 1876.21  5432.7 1878.34  5460.7 1879.76
#Mann=7,-1,0
  4447.5    0.07       0  4581.9   0.035       0  4940.9    0.07       0
  4980.7    0.05       0  4998.6    0.07       0  5035.3   0.033       0
  5405.7     0.1       0
Bank Sta=4980.7,4998.6
Exp/Cntr=0.3,0.1

Type RM Length L Ch R = 1,17669,416,416,416
BEGIN DESCRIPTION:
Palmer Creek 30.0
END DESCRIPTION:
XS GIS Cut Line= 3
      1914925.03     13874724.97      1915225.00     13874475.00
      1915325.01     13873974.97
#Sta/Elev= 30
  4609.6 1754.02  4675.2 1751.42  4758.6 1745.75  4857.5 1743.31  4894.0 1743.61
  4957.8 1741.45  4964.3 1737.38  4977.4 1732.47  4977.9 1731.97  4995.4 1732.47
  5057.0 1732.65  5142.8 1732.85  5183.6 1734.04  5234.6 1741.39  5265.2 1746.75
  5275.4 1749.49  5285.6 1755.43  5306.0 1763.27  5326.4 1774.03  5336.6 1782.12
  5377.4 1803.42  5389.2 1812.95  5408.0 1824.83  5418.2 1833.02  5428.4 1837.15
  5438.6 1845.91  5469.2 1857.19  5479.4 1865.15  5489.6 1871.33  5510.0 1872.00
#Mann=6,-1,0
  4609.6    0.07       0  4675.2   0.035       0  4977.4   0.035       0
  4995.4   0.035       0  5057.0   0.033       0  5389.2     0.1       0
Bank Sta=4977.4,4995.4
Exp/Cntr=0.3,0.1

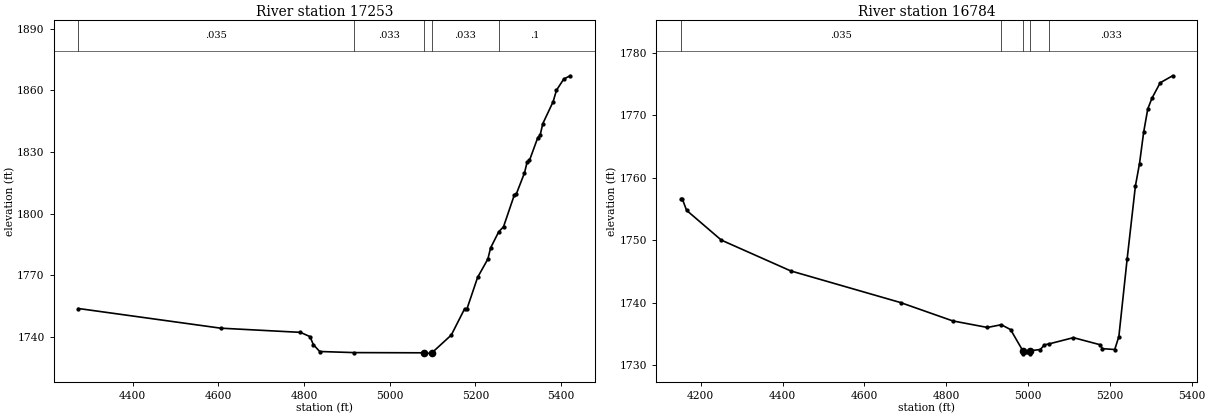
Type RM Length L Ch R = 1,17253,469,469,469
BEGIN DESCRIPTION:
Palmer Creek 29.0
END DESCRIPTION:
XS GIS Cut Line= 3
      1915125.01     13875024.98      1915525.00     13874425.00
      1915375.00     13874024.99
#Sta/Elev= 30
  4273.2 1753.71  4605.2 1744.13  4791.5 1742.09  4814.0 1740.00  4821.5 1736.16
  4836.5 1732.76  4917.3 1732.22  5080.5 1732.12  5081.0 1731.62  5098.5 1732.12
  5143.8 1740.78  5175.0 1753.62  5180.3 1753.49  5205.2 1768.89  5229.2 1777.83
  5235.5 1783.23  5254.5 1791.10  5265.7 1793.54  5290.7 1808.90  5296.0 1809.73
  5314.7 1819.82  5320.9 1825.13  5326.3 1825.90  5345.8 1837.03  5351.2 1838.16
  5357.4 1843.79  5381.4 1854.45  5389.4 1860.10  5406.4 1865.56  5421.5 1867.14
#Mann=5,-1,0
  4273.2   0.035       0  4917.3   0.033       0  5080.5   0.033       0
  5098.5   0.033       0  5254.5     0.1       0
Bank Sta=5080.5,5098.5
Exp/Cntr=0.3,0.1

Type RM Length L Ch R = 1,16784,916,916,916
BEGIN DESCRIPTION:
Palmer Creek 28.0
END DESCRIPTION:
XS GIS Cut Line= 3
      1915274.99     13875175.01      1915875.00     13874575.00
      1915825.00     13874224.99
#Sta/Elev= 30
  4151.1 1756.63  4154.6 1756.63  4165.3 1754.77  4250.1 1750.01  4419.8 1745.08
  4688.5 1740.01  4815.8 1737.08  4900.6 1736.03  4934.5 1736.47  4957.2 1735.69
  4987.1 1732.31  4987.6 1731.81  5004.6 1731.81  5005.1 1732.31  5029.9 1732.50
  5040.0 1733.25  5051.2 1733.40  5110.8 1734.40  5176.4 1733.26  5181.5 1732.64
  5211.8 1732.50  5221.9 1734.58  5242.1 1746.96  5262.3 1758.65  5272.4 1762.26
  5282.5 1767.27  5292.6 1771.00  5302.7 1772.70  5322.9 1775.18  5353.2 1776.30
#Mann=5,-1,0
  4151.1   0.035       0  4934.5     0.1       0  4987.1    0.05       0
  5005.1     0.1       0  5051.2   0.033       0
Bank Sta=4987.1,5005.1
Exp/Cntr=0.3,0.1