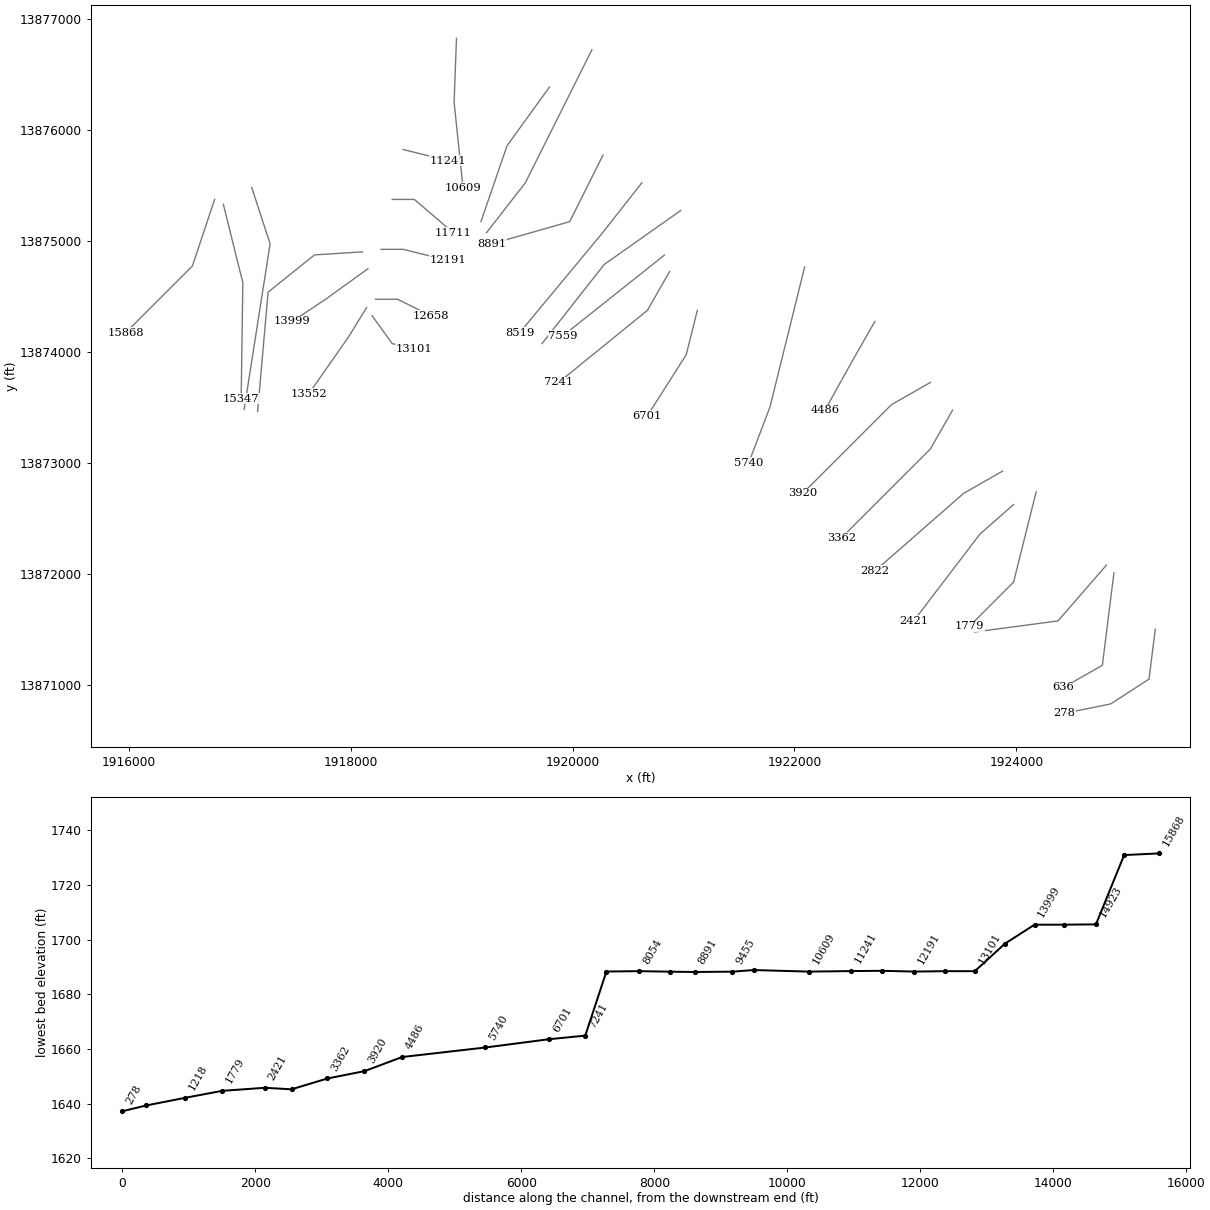
HEC-RAS study Palmer Creek.prj: Palmer Creek Base Level Engineering

--- Palmer Creek.g01 (geometry) --- (continued)

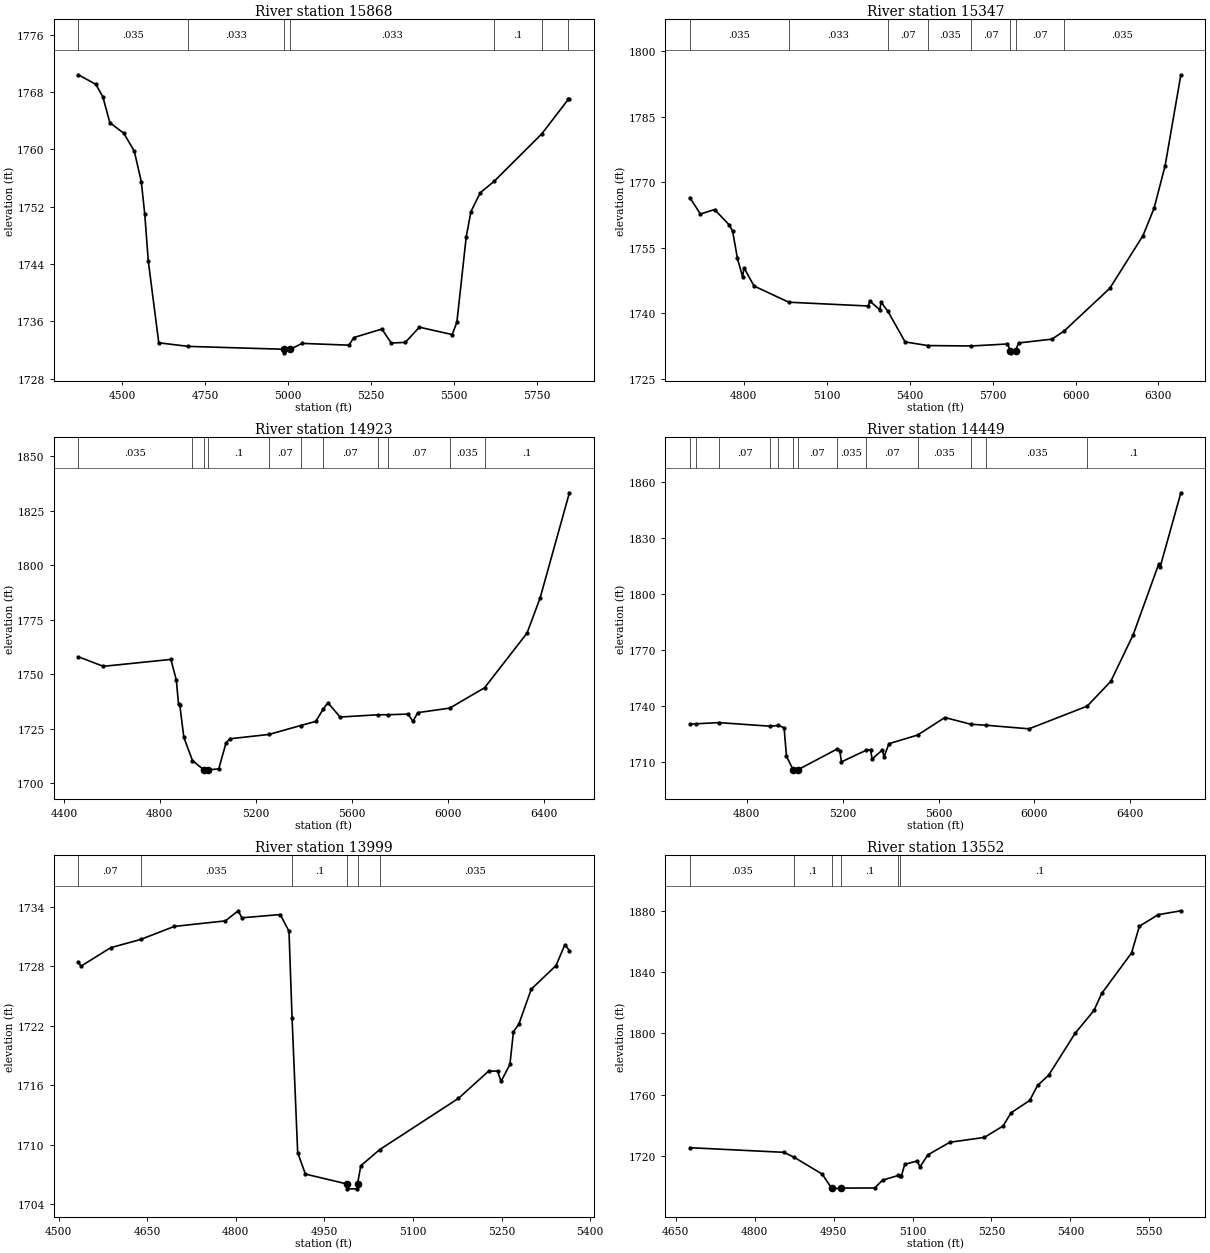
Type RM Length L Ch R = 1,15868,521,521,521
BEGIN DESCRIPTION:
Palmer Creek 27.0
END DESCRIPTION:
XS GIS Cut Line= 3
      1916774.99     13875374.96      1916575.00     13874775.00
      1915975.03     13874175.03
#Sta/Elev= 30
  4367.8 1770.43  4420.5 1769.09  4441.5 1767.36  4462.6 1763.75  4504.8 1762.26
  4536.4 1759.76  4557.5 1755.50  4568.0 1750.95  4578.6 1744.41  4610.2 1733.01
  4699.7 1732.51  4988.3 1732.11  4988.8 1731.61  5006.8 1732.11  5042.6 1732.93
  5184.1 1732.68  5198.2 1733.74  5283.1 1734.93  5311.3 1732.98  5353.8 1733.07
  5396.2 1735.19  5495.2 1734.16  5509.3 1735.88  5537.6 1747.84  5551.8 1751.34
  5580.0 1753.97  5621.5 1755.55  5765.2 1762.17  5845.7 1767.02  5848.7 1767.02
#Mann=7,-1,0
  4367.8   0.035       0  4699.7   0.033       0  4988.3   0.033       0
  5006.8   0.033       0  5621.5     0.1       0  5765.2    0.07       0
  5845.7     0.1       0
Bank Sta=4988.3,5006.8
Exp/Cntr=0.3,0.1

Type RM Length L Ch R = 1,15347,424,424,424
BEGIN DESCRIPTION:
Palmer Creek 26.0
END DESCRIPTION:
XS GIS Cut Line= 4
      1916853.43     13875331.90      1916959.77     13874902.18
      1917029.22     13874624.40      1917014.06     13873578.13
#Sta/Elev= 30
  4605.5 1766.48  4643.5 1762.72  4695.0 1763.74  4746.5 1760.32  4759.9 1758.89
  4777.4 1752.60  4796.1 1748.38  4801.3 1750.44  4837.5 1746.27  4963.2 1742.57
  5250.8 1741.70  5255.9 1742.85  5292.0 1740.85  5297.2 1742.55  5321.5 1740.49
  5383.9 1733.49  5466.1 1732.66  5623.8 1732.57  5754.0 1733.02  5764.7 1731.50
  5765.2 1731.00  5783.2 1731.50  5794.0 1733.26  5914.0 1734.12  5957.9 1735.93
  6124.0 1745.75  6244.0 1757.79  6284.0 1764.04  6324.0 1773.77  6380.9 1794.54
#Mann=8,-1,0
  4605.5   0.035       0  4963.2   0.033       0  5321.5    0.07       0
  5466.1   0.035       0  5623.8    0.07       0  5764.7   0.033       0
  5783.2    0.07       0  5957.9   0.035       0
Bank Sta=5764.7,5783.2
Exp/Cntr=0.3,0.1

Type RM Length L Ch R = 1,14923,474,474,474
BEGIN DESCRIPTION:
Palmer Creek 25.0
END DESCRIPTION:
XS GIS Cut Line= 3
      1917109.10     13875483.02      1917275.00     13874975.00
      1917040.92     13873480.34
#Sta/Elev= 30
  4460.6 1757.98  4564.6 1753.62  4846.3 1756.79  4868.8 1747.34  4878.2 1736.26
  4883.4 1735.81  4900.3 1721.00  4936.3 1710.34  4983.1 1706.15  4983.6 1705.65
  5001.6 1706.15  5045.6 1706.52  5076.0 1718.40  5091.6 1720.36  5254.8 1722.35
  5386.7 1726.43  5450.5 1728.35  5480.7 1733.90  5501.1 1736.89  5551.7 1730.35
  5708.5 1731.37  5750.6 1731.41  5835.1 1731.68  5855.4 1728.36  5875.6 1732.36
  6008.8 1734.44  6154.2 1743.78  6331.1 1768.85  6385.7 1784.96  6507.9 1833.27
#Mann=11,-1,0
  4460.6   0.035       0  4936.3     0.1       0  4983.1    0.05       0
  5001.6     0.1       0  5254.8    0.07       0  5386.7   0.035       0
  5480.7    0.07       0  5708.5   0.035       0  5750.6    0.07       0
  6008.8   0.035       0  6154.2     0.1       0
Bank Sta=4983.1,5001.6
Exp/Cntr=0.3,0.1

Type RM Length L Ch R = 1,14449,450,450,450
BEGIN DESCRIPTION:
Palmer Creek 24.0
END DESCRIPTION:
XS GIS Cut Line= 4
      1918107.48     13874902.51      1917675.00     13874875.00
      1917256.75     13874538.95      1917162.36     13873463.66
#Sta/Elev= 30
  4562.1 1730.46  4588.0 1730.69  4682.8 1731.32  4898.0 1729.39  4932.0 1729.80
  4955.4 1728.60  4965.4 1713.28  4993.4 1706.04  4993.9 1705.54  5011.9 1706.04
  5174.7 1717.06  5187.9 1716.39  5194.7 1710.33  5298.0 1716.56  5316.2 1716.91
  5322.7 1711.85  5365.8 1716.70  5372.3 1713.00  5393.1 1720.06  5512.6 1724.66
  5626.3 1734.05  5734.0 1730.46  5799.7 1729.90  5977.6 1728.00  6220.5 1740.13
  6318.9 1753.38  6412.0 1778.16  6519.4 1816.24  6524.4 1814.26  6611.4 1854.17
#Mann=13,-1,0
  4562.1    0.07       0  4588.0   0.035       0  4682.8    0.07       0
  4898.0     0.1       0  4932.0    0.07       0  4993.4    0.05       0
  5011.9    0.07       0  5174.7   0.035       0  5298.0    0.07       0
  5512.6   0.035       0  5734.0    0.07       0  5799.7   0.035       0
  6220.5     0.1       0
Bank Sta=4993.4,5011.9
Exp/Cntr=0.3,0.1

Type RM Length L Ch R = 1,13999,447,447,447
BEGIN DESCRIPTION:
Palmer Creek 23.0
END DESCRIPTION:
XS GIS Cut Line= 3
      1918156.76     13874750.18      1917775.00     13874475.00
      1917474.96     13874274.97
#Sta/Elev= 30
  4533.5 1728.44  4537.8 1728.02  4588.1 1729.89  4638.7 1730.72  4695.9 1732.04
  4782.2 1732.60  4804.1 1733.62  4810.2 1732.91  4875.2 1733.24  4890.0 1731.55
  4895.2 1722.80  4904.7 1709.19  4917.8 1707.02  4987.5 1706.03  4988.0 1705.53
  5005.5 1705.53  5006.0 1706.03  5011.6 1707.86  5043.5 1709.49  5176.9 1714.67
  5227.9 1717.42  5243.0 1717.43  5249.0 1716.38  5264.0 1718.10  5270.0 1721.42
  5279.0 1722.15  5300.1 1725.70  5342.1 1728.09  5357.1 1730.20  5364.7 1729.60
#Mann=6,-1,0
  4533.5    0.07       0  4638.7   0.035       0  4895.2     0.1       0
  4987.5    0.05       0  5006.0     0.1       0  5043.5   0.035       0
Bank Sta=4987.5,5006
Exp/Cntr=0.3,0.1

Type RM Length L Ch R = 1,13552,451,451,451
BEGIN DESCRIPTION:
Palmer Creek 22.0
END DESCRIPTION:
XS GIS Cut Line= 3
      1918144.64     13874399.96      1917975.00     13874125.00
      1917625.00     13873625.00
#Sta/Elev= 30
  4676.7 1725.40  4854.9 1722.39  4874.3 1719.28  4928.3 1708.16  4946.1 1699.07
  4946.6 1698.57  4964.7 1699.07  5028.1 1699.13  5042.9 1704.21  5073.2 1707.34
  5075.7 1707.04  5078.7 1706.69  5085.2 1714.57  5108.3 1716.68  5114.4 1713.03
  5129.3 1720.78  5171.1 1728.96  5236.5 1732.09  5272.2 1739.58  5287.1 1748.07
  5322.8 1756.24  5337.6 1766.00  5358.6 1772.60  5409.1 1800.02  5444.9 1814.88
  5459.7 1826.03  5516.4 1852.40  5531.2 1869.80  5566.9 1877.33  5610.1 1879.89
#Mann=6,-1,0
  4676.7   0.035       0  4874.3     0.1       0  4946.1    0.05       0
  4964.7     0.1       0  5073.2    0.07       0  5075.7     0.1       0
Bank Sta=4946.1,4964.7
Exp/Cntr=0.3,0.1

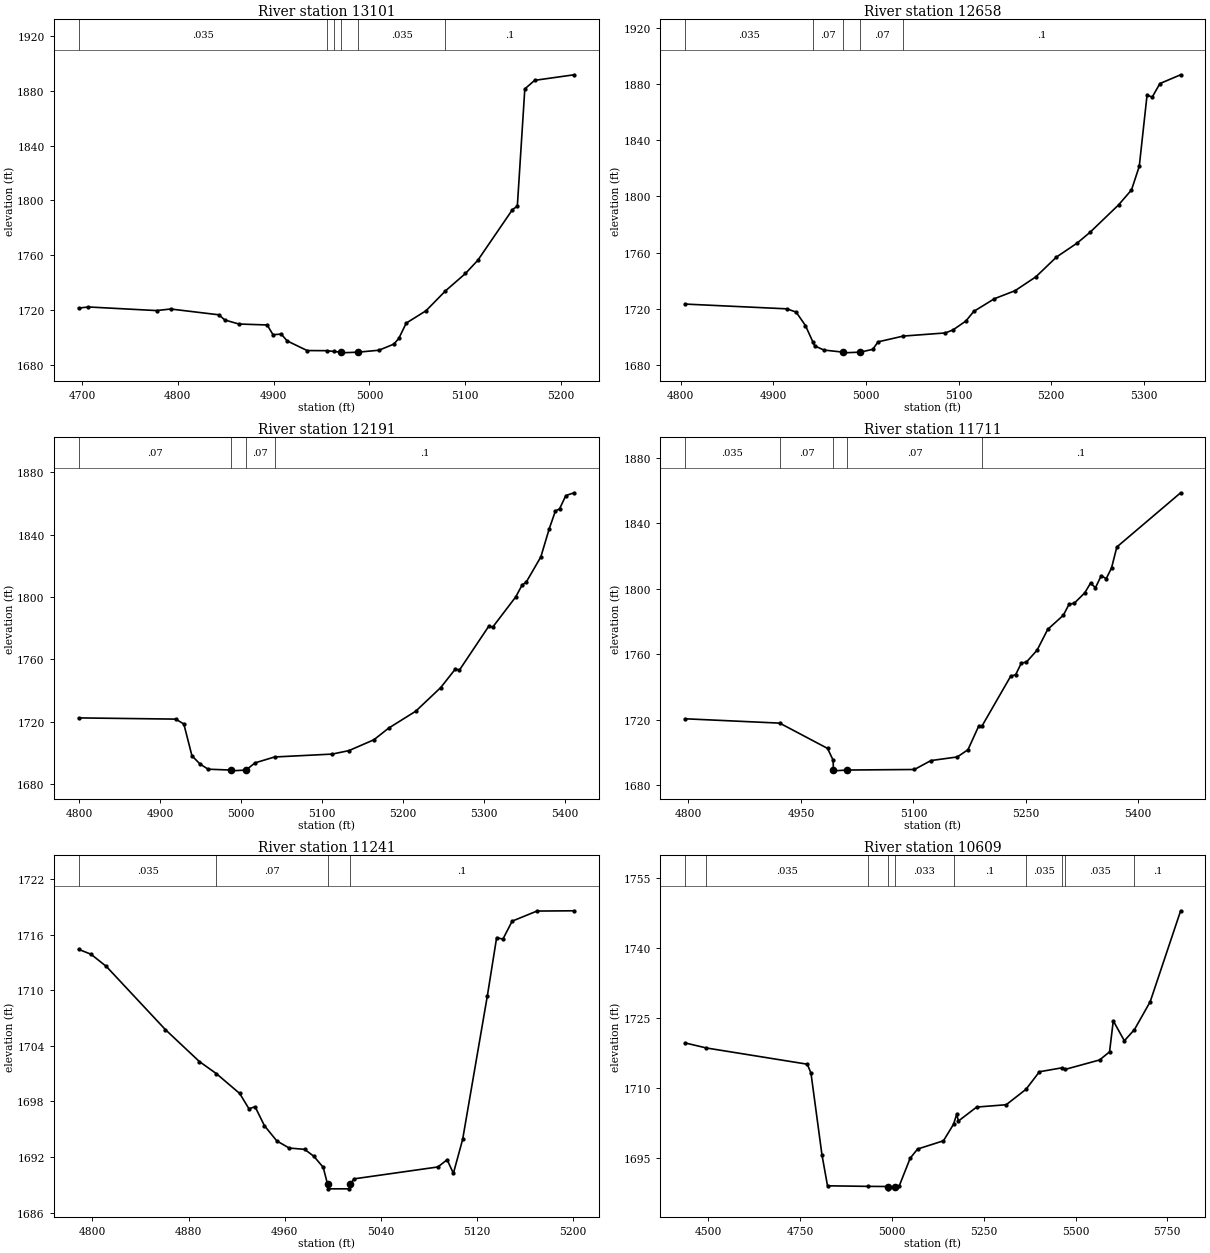
Type RM Length L Ch R = 1,13101,443,443,443
BEGIN DESCRIPTION:
Palmer Creek 21.0
END DESCRIPTION:
XS GIS Cut Line= 3
      1918193.53     13874327.37      1918375.00     13874075.00
      1918575.00     13874025.00
#Sta/Elev= 30
  4696.6 1721.23  4706.7 1722.06  4777.9 1719.42  4792.6 1720.57  4842.9 1716.33
  4849.1 1712.54  4863.8 1709.60  4893.3 1708.90  4899.4 1701.79  4908.0 1702.22
  4914.1 1697.27  4935.0 1690.20  4955.7 1690.10  4963.1 1689.52  4969.9 1689.03
  4970.4 1688.53  4988.5 1689.03  5010.0 1690.45  5025.5 1694.92  5030.6 1699.04
  5038.4 1710.27  5059.0 1719.27  5079.3 1733.80  5100.2 1746.54  5113.1 1756.21
  5149.2 1793.21  5154.3 1795.71  5162.1 1881.45  5172.4 1887.71  5213.6 1891.77
#Mann=6,-1,0
  4696.6   0.035       0  4955.7    0.07       0  4963.1   0.035       0
  4969.9   0.035       0  4988.5   0.035       0  5079.3     0.1       0
Bank Sta=4969.9,4988.5
Exp/Cntr=0.3,0.1

Type RM Length L Ch R = 1,12658,467,467,467
BEGIN DESCRIPTION:
Palmer Creek 20.0
END DESCRIPTION:
XS GIS Cut Line= 3
      1918225.00     13874475.00      1918425.00     13874475.00
      1918724.99     13874325.00
#Sta/Elev= 30
  4804.6 1723.27  4914.6 1719.87  4924.6 1717.54  4934.6 1708.00  4942.7 1696.24
  4944.6 1693.48  4954.6 1690.51  4975.2 1689.03  4975.7 1688.53  4993.9 1689.03
  5007.4 1691.02  5013.0 1696.34  5040.4 1700.48  5085.7 1702.70  5094.0 1704.83
  5108.0 1711.20  5116.4 1718.00  5138.8 1727.09  5161.1 1732.79  5183.5 1742.63
  5205.8 1756.75  5228.2 1766.72  5242.2 1774.45  5272.9 1793.90  5286.9 1804.56
  5295.3 1821.40  5303.7 1872.09  5309.3 1870.72  5317.6 1880.36  5340.0 1886.61
#Mann=5,-1,0
  4804.6   0.035       0  4942.7    0.07       0  4975.2    0.05       0
  4993.9    0.07       0  5040.4     0.1       0
Bank Sta=4975.2,4993.9
Exp/Cntr=0.3,0.1

Type RM Length L Ch R = 1,12191,480,480,480
BEGIN DESCRIPTION:
Palmer Creek 19.0
END DESCRIPTION:
XS GIS Cut Line= 3
      1918275.01     13874925.00      1918475.00     13874925.00
      1918875.00     13874825.00
#Sta/Elev= 30
  4799.6 1722.35  4919.6 1721.57  4929.6 1718.42  4939.6 1698.05  4949.6 1692.75
  4959.6 1689.43  4987.7 1688.88  4988.2 1688.38  5006.4 1688.88  5017.6 1693.50
  5041.7 1697.27  5113.0 1699.13  5133.6 1701.36  5164.5 1708.33  5182.6 1715.76
  5216.1 1726.63  5247.0 1741.81  5265.0 1753.66  5270.2 1753.09  5306.2 1781.04
  5311.4 1780.69  5339.7 1800.00  5347.5 1807.56  5352.6 1809.41  5370.7 1825.64
  5381.0 1843.57  5388.7 1855.08  5393.9 1856.54  5401.6 1865.03  5411.9 1866.80
#Mann=4,-1,0
  4799.6    0.07       0  4987.7    0.05       0  5006.4    0.07       0
  5041.7     0.1       0
Bank Sta=4987.7,5006.4
Exp/Cntr=0.3,0.1

Type RM Length L Ch R = 1,11711,470,470,470
BEGIN DESCRIPTION:
Palmer Creek 18.0
END DESCRIPTION:
XS GIS Cut Line= 3
      1918374.98     13875375.00      1918575.00     13875375.00
      1918925.00     13875075.00
#Sta/Elev= 30
  4795.5 1720.51  4921.7 1717.85  4985.5 1702.39  4993.0 1695.12  4993.3 1689.16
  4993.8 1688.66  5012.0 1689.16  5101.4 1689.48  5123.4 1694.94  5158.5 1697.15
  5172.8 1701.56  5187.0 1715.89  5191.5 1716.05  5229.8 1746.55  5236.4 1747.47
  5244.1 1754.63  5250.7 1755.15  5265.0 1762.46  5279.2 1775.21  5300.1 1783.87
  5307.8 1790.73  5314.4 1791.09  5328.6 1797.55  5336.3 1803.47  5342.9 1800.71
  5350.6 1808.07  5357.2 1806.22  5364.3 1812.74  5371.4 1825.61  5456.5 1858.77
#Mann=5,-1,0
  4795.5   0.035       0  4921.7    0.07       0  4993.3    0.05       0
  5012.0    0.07       0  5191.5     0.1       0
Bank Sta=4993.3,5012
Exp/Cntr=0.3,0.1

Type RM Length L Ch R = 1,11241,632,632,632
BEGIN DESCRIPTION:
Palmer Creek 17.0
END DESCRIPTION:
XS GIS Cut Line= 3
      1918475.05     13875824.99      1918675.00     13875775.00
      1918875.04     13875724.99
#Sta/Elev= 30
  4788.5 1714.41  4798.8 1713.88  4811.6 1712.56  4860.6 1705.76  4889.0 1702.30
  4903.1 1701.00  4922.5 1698.86  4930.2 1697.21  4935.3 1697.43  4943.1 1695.38
  4953.4 1693.74  4963.7 1692.97  4976.6 1692.83  4984.3 1692.07  4992.0 1690.89
  4995.6 1689.07  4996.1 1688.57  5013.8 1688.57  5014.3 1689.07  5017.8 1689.65
  5087.4 1690.93  5095.1 1691.71  5100.3 1690.24  5108.0 1693.90  5128.6 1709.42
  5136.3 1715.68  5141.5 1715.51  5149.2 1717.45  5169.8 1718.54  5200.8 1718.57
#Mann=4,-1,0
  4788.5   0.035       0  4903.1    0.07       0  4995.6    0.05       0
  5014.3     0.1       0
Bank Sta=4995.6,5014.3
Exp/Cntr=0.3,0.1

Type RM Length L Ch R = 1,10609,835,835,835
BEGIN DESCRIPTION:
Palmer Creek 16.0
END DESCRIPTION:
XS GIS Cut Line= 3
      1918954.44     13876827.52      1918933.00     13876251.86
      1919013.06     13875482.48
#Sta/Elev= 30
  4436.7 1719.65  4494.6 1718.57  4769.5 1715.09  4779.5 1713.18  4809.5 1695.63
  4824.6 1689.02  4934.7 1688.90  4989.8 1688.87  4990.3 1688.37  5009.5 1688.87
  5019.7 1688.96  5049.8 1694.95  5069.9 1696.90  5140.3 1698.67  5167.7 1702.21
  5176.3 1704.33  5181.3 1702.92  5230.8 1705.90  5311.2 1706.40  5364.9 1709.69
  5401.7 1713.47  5463.5 1714.32  5472.0 1713.98  5565.6 1716.00  5592.7 1717.74
  5602.8 1724.38  5633.0 1720.11  5660.6 1722.52  5703.3 1728.47  5786.3 1747.98
#Mann=10,-1,0
  4436.7    0.07       0  4494.6   0.035       0  4934.7   0.033       0
  4989.8   0.033       0  5009.5   0.033       0  5167.7     0.1       0
  5364.9   0.035       0  5463.5     0.1       0  5472.0   0.035       0
  5660.6     0.1       0
Bank Sta=4989.8,5009.5
Exp/Cntr=0.3,0.1

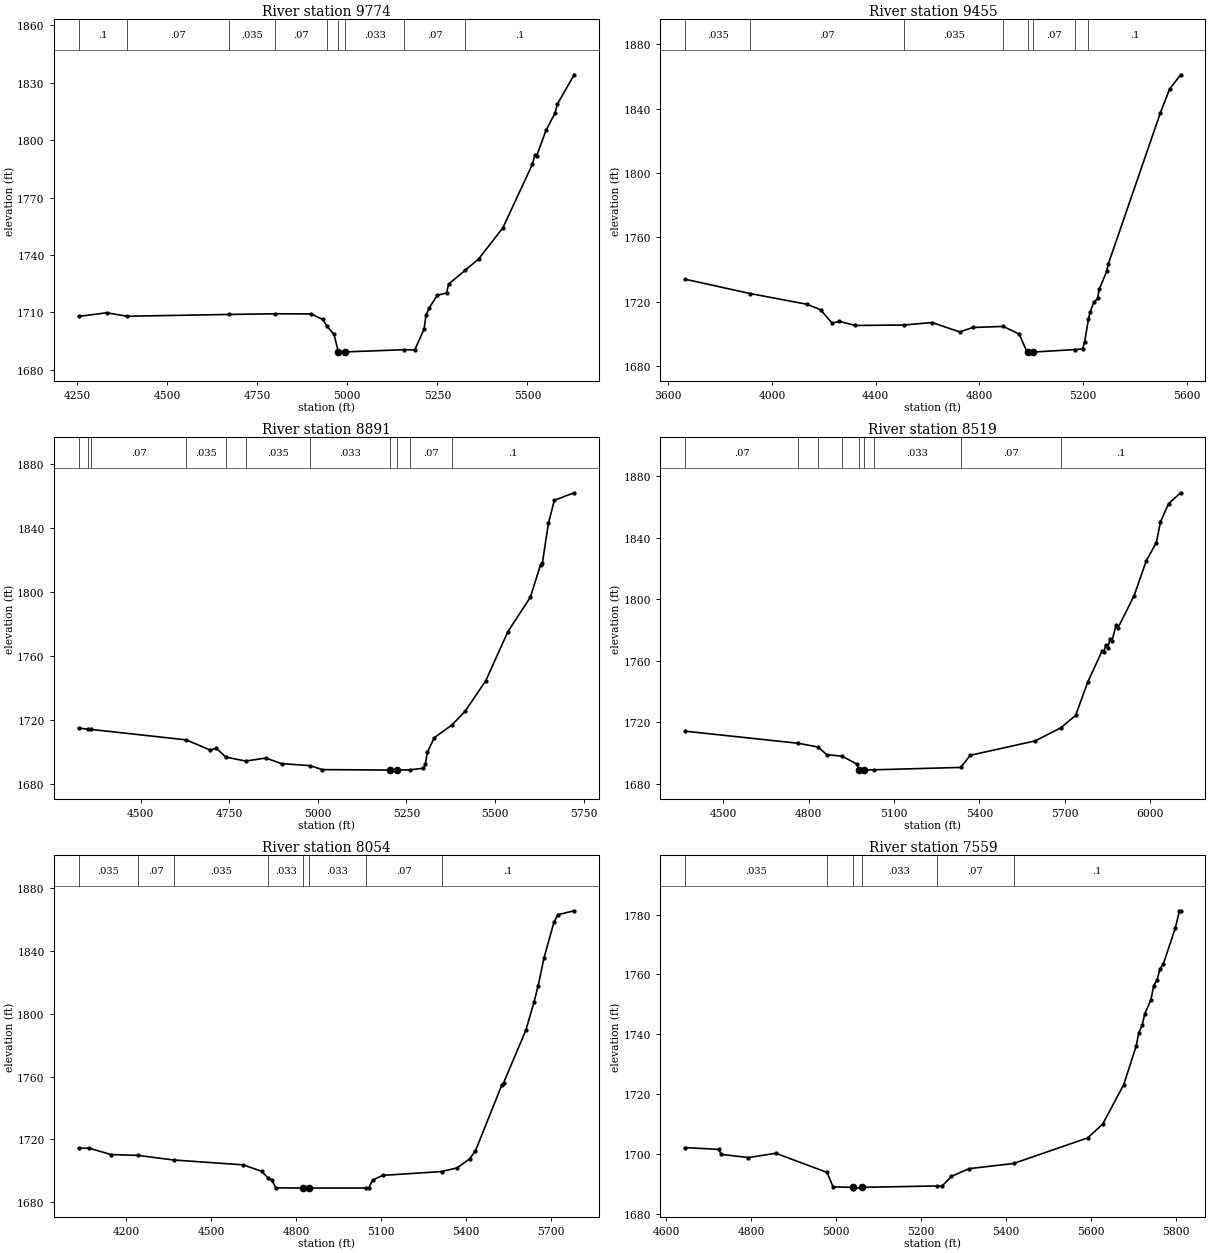
Type RM Length L Ch R = 1,9774,319,319,319
BEGIN DESCRIPTION:
Palmer Creek 15.0
END DESCRIPTION:
XS GIS Cut Line= 3
      1919792.20     13876387.82      1919409.94     13875858.93
      1919175.01     13875175.03
#Sta/Elev= 30
  4254.2 1707.95  4332.1 1709.86  4388.9 1708.05  4671.2 1708.98  4800.1 1709.32
  4899.3 1709.25  4932.1 1706.35  4944.1 1702.71  4963.3 1698.58  4975.1 1689.44
  4975.6 1688.94  4994.8 1689.44  5158.1 1690.57  5187.4 1690.48  5213.3 1701.42
  5218.6 1708.74  5228.1 1712.56  5249.9 1719.00  5275.8 1720.19  5281.1 1724.78
  5327.3 1732.03  5364.3 1737.87  5432.1 1754.23  5513.6 1787.25  5520.6 1791.97
  5525.8 1791.79  5551.8 1805.13  5577.1 1814.18  5583.1 1818.74  5629.9 1834.08
#Mann=9,-1,0
  4254.2     0.1       0  4388.9    0.07       0  4671.2   0.035       0
  4800.1    0.07       0  4944.1   0.033       0  4975.1   0.033       0
  4994.8   0.033       0  5158.1    0.07       0  5327.3     0.1       0
Bank Sta=4975.1,4994.8
Exp/Cntr=0.3,0.1

Type RM Length L Ch R = 1,9455,564,564,564
BEGIN DESCRIPTION:
Palmer Creek 14.0
END DESCRIPTION:
XS GIS Cut Line= 3
      1920175.02     13876725.04      1919575.00     13875525.00
      1919224.98     13875074.98
#Sta/Elev= 30
  3664.7 1734.08  3916.8 1725.14  4134.3 1718.54  4187.4 1715.09  4232.1 1706.77
  4260.1 1707.91  4321.6 1705.35  4509.2 1705.64  4617.9 1707.17  4724.1 1701.33
  4774.4 1704.09  4891.9 1704.76  4953.3 1700.05  4984.0 1688.89  4988.1 1688.85
  4988.6 1688.35  5007.8 1688.85  5168.0 1690.37  5198.2 1690.82  5206.4 1695.34
  5220.9 1709.36  5227.2 1713.73  5241.7 1719.72  5256.1 1722.18  5262.5 1727.88
  5291.4 1739.02  5297.8 1743.71  5498.6 1837.54  5533.9 1852.20  5576.5 1861.06
#Mann=8,-1,0
  3664.7   0.035       0  3916.8    0.07       0  4509.2   0.035       0
  4891.9    0.07       0  4988.1   0.033       0  5007.8    0.07       0
  5168.0    0.07       0  5220.9     0.1       0
Bank Sta=4988.1,5007.8
Exp/Cntr=0.3,0.1

Type RM Length L Ch R = 1,8891,372,372,372
BEGIN DESCRIPTION:
Palmer Creek 13.0
END DESCRIPTION:
XS GIS Cut Line= 3
      1920275.00     13875775.00      1919975.00     13875175.00
      1919275.03     13874975.01
#Sta/Elev= 30
  4324.8 1714.99  4351.4 1714.29  4359.0 1714.18  4628.6 1707.61  4696.5 1701.19
  4713.3 1702.38  4740.0 1696.85  4796.1 1694.36  4853.1 1696.23  4897.8 1692.75
  4978.3 1691.48  5012.5 1688.99  5204.0 1688.73  5204.5 1688.23  5224.1 1688.73
  5260.3 1688.84  5297.2 1689.85  5303.7 1692.28  5308.9 1699.74  5328.4 1708.90
  5379.0 1717.03  5415.5 1725.42  5474.0 1744.60  5536.4 1775.30  5600.1 1797.00
  5628.7 1817.28  5633.9 1818.29  5650.8 1843.06  5667.7 1857.58  5723.6 1862.28
#Mann=11,-1,0
  4324.8    0.07       0  4351.4   0.035       0  4359.0    0.07       0
  4628.6   0.035       0  4740.0    0.07       0  4796.1   0.035       0
  4978.3   0.033       0  5204.0   0.033       0  5224.1   0.033       0
  5260.3    0.07       0  5379.0     0.1       0
Bank Sta=5204,5224.1
Exp/Cntr=0.3,0.1

Type RM Length L Ch R = 1,8519,465,465,465
BEGIN DESCRIPTION:
Palmer Creek 12.0
END DESCRIPTION:
XS GIS Cut Line= 3
      1920625.01     13875525.01      1920266.76     13875069.14
      1919524.98     13874174.97
#Sta/Elev= 30
  4365.9 1714.15  4764.2 1706.26  4832.6 1703.86  4863.9 1698.88  4917.5 1697.88
  4971.3 1692.60  4975.5 1688.84  4976.0 1688.34  4995.7 1688.84  5028.8 1689.01
  5334.2 1690.56  5368.4 1698.47  5596.3 1707.83  5686.3 1716.32  5738.3 1724.41
  5781.3 1746.22  5830.7 1766.04  5837.2 1765.45  5845.1 1770.53  5851.6 1768.45
  5859.4 1774.30  5865.9 1772.72  5880.2 1782.93  5886.7 1781.16  5944.0 1802.34
  5987.0 1825.19  6022.2 1836.86  6036.5 1850.30  6065.1 1862.20  6107.5 1869.29
#Mann=9,-1,0
  4365.9    0.07       0  4764.2   0.035       0  4832.6    0.07       0
  4917.5   0.035       0  4975.5   0.035       0  4995.7   0.035       0
  5028.8   0.033       0  5334.2    0.07       0  5686.3     0.1       0
Bank Sta=4975.5,4995.7
Exp/Cntr=0.3,0.1

Type RM Length L Ch R = 1,8054,495,495,495
BEGIN DESCRIPTION:
Palmer Creek 11.0
END DESCRIPTION:
XS GIS Cut Line= 3
      1920974.97     13875274.98      1920285.47     13874788.38
      1919725.02     13874075.02
#Sta/Elev= 30
  4031.5 1714.37  4068.2 1714.47  4146.0 1710.34  4240.1 1709.84  4367.3 1706.89
  4612.7 1703.82  4677.9 1699.71  4702.0 1695.23  4713.6 1694.28  4728.4 1689.17
  4825.4 1689.04  4825.9 1688.54  4845.6 1689.04  5046.4 1689.06  5056.9 1689.13
  5070.5 1694.16  5106.6 1697.11  5313.8 1699.54  5369.3 1701.87  5413.0 1707.60
  5433.8 1712.78  5526.8 1754.53  5533.2 1756.00  5611.8 1789.43  5640.7 1807.37
  5655.2 1817.72  5676.0 1835.50  5711.2 1858.22  5725.7 1863.03  5782.6 1865.48
#Mann=8,-1,0
  4031.5   0.035       0  4240.1    0.07       0  4367.3   0.035       0
  4702.0   0.033       0  4825.4   0.033       0  4845.6   0.033       0
  5046.4    0.07       0  5313.8     0.1       0
Bank Sta=4825.4,4845.6
Exp/Cntr=0.3,0.1

Type RM Length L Ch R = 1,7559,318,318,318
BEGIN DESCRIPTION:
Mapping XS 2aafdd98
END DESCRIPTION:
XS GIS Cut Line= 2
      1920827.27     13874872.39      1919915.41     13874146.68
#Sta/Elev= 30
  4644.7 1702.18  4723.4 1701.58  4729.8 1699.91  4793.8 1698.84  4857.9 1700.29
  4978.6 1693.88  4992.7 1689.04  5040.0 1688.90  5040.5 1688.40  5060.2 1688.90
  5236.0 1689.36  5248.7 1689.27  5271.1 1692.57  5312.8 1695.14  5417.2 1696.87
  5591.5 1705.42  5626.7 1710.01  5676.4 1723.24  5705.2 1735.95  5711.6 1740.48
  5719.6 1743.00  5726.0 1746.95  5740.4 1751.63  5746.8 1756.27  5754.9 1758.26
  5761.2 1761.80  5769.3 1763.43  5797.8 1775.67  5807.4 1781.28  5810.1 1781.28
#Mann=6,-1,0
  4644.7   0.035       0  4978.6   0.033       0  5040.0   0.033       0
  5060.2   0.033       0  5236.0    0.07       0  5417.2     0.1       0
Bank Sta=5040,5060.2
Exp/Cntr=0.3,0.1

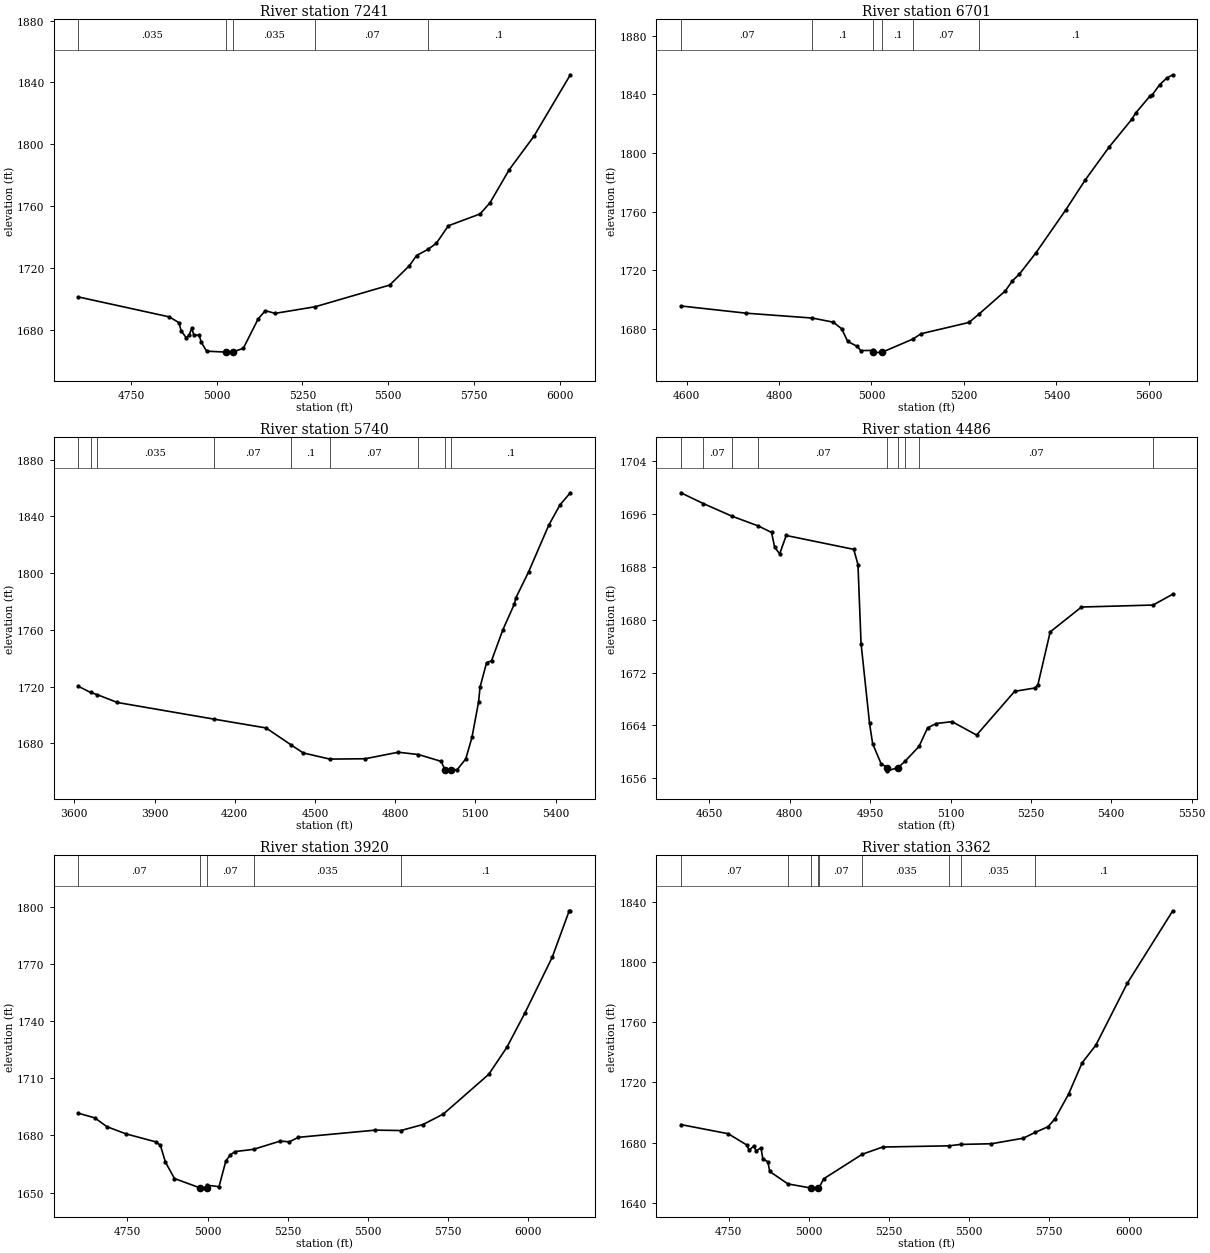
Type RM Length L Ch R = 1,7241,540,540,540
BEGIN DESCRIPTION:
Palmer Creek 10.0
END DESCRIPTION:
XS GIS Cut Line= 3
      1920874.98     13874724.97      1920675.00     13874375.00
      1919874.96     13873724.97
#Sta/Elev= 30
  4596.9 1701.11  4861.8 1688.22  4889.8 1684.48  4896.3 1679.19  4911.4 1674.62
  4919.4 1676.30  4927.3 1680.93  4933.0 1676.54  4948.9 1676.38  4954.6 1671.92
  4970.5 1666.02  5025.8 1665.45  5026.3 1664.95  5046.1 1665.45  5077.5 1667.88
  5120.6 1686.85  5141.7 1692.23  5170.2 1690.50  5287.3 1694.79  5504.2 1708.82
  5561.7 1721.39  5582.5 1727.94  5615.5 1731.88  5640.0 1735.79  5675.2 1747.19
  5767.9 1754.87  5796.6 1762.08  5852.6 1783.47  5924.5 1805.10  6030.8 1844.91
#Mann=5,-1,0
  4596.9   0.035       0  5025.8   0.035       0  5046.1   0.035       0
  5287.3    0.07       0  5615.5     0.1       0
Bank Sta=5025.8,5046.1
Exp/Cntr=0.3,0.1

Type RM Length L Ch R = 1,6701,961,961,961
BEGIN DESCRIPTION:
Palmer Creek 9.0
END DESCRIPTION:
XS GIS Cut Line= 3
      1921125.00     13874375.01      1921025.00     13873975.00
      1920675.02     13873425.03
#Sta/Elev= 30
  4587.7 1695.64  4729.4 1690.70  4872.4 1687.38  4917.6 1684.56  4935.6 1680.04
  4948.5 1671.49  4969.1 1668.04  4976.8 1665.22  5003.0 1665.29  5003.4 1664.15
  5003.9 1663.65  5023.7 1664.15  5089.5 1673.04  5107.5 1676.70  5210.8 1684.38
  5232.1 1689.96  5289.6 1705.94  5304.8 1712.77  5320.1 1717.42  5355.6 1731.82
  5420.0 1761.04  5462.3 1781.58  5513.9 1804.01  5563.0 1822.99  5571.5 1827.29
  5602.0 1838.71  5607.9 1839.93  5623.2 1846.54  5638.4 1851.11  5651.9 1853.44
#Mann=6,-1,0
  4587.7    0.07       0  4872.4     0.1       0  5003.4    0.05       0
  5023.7     0.1       0  5089.5    0.07       0  5232.1     0.1       0
Bank Sta=5003.4,5023.7
Exp/Cntr=0.3,0.1

Type RM Length L Ch R = 1,5740,1254,1254,1254
BEGIN DESCRIPTION:
Palmer Creek 8.1
END DESCRIPTION:
XS GIS Cut Line= 3
      1922092.01     13874766.04      1921779.22     13873502.44
      1921587.77     13872999.38
#Sta/Elev= 30
  3615.5 1720.14  3661.2 1715.82  3685.1 1714.34  3760.8 1708.79  4122.3 1697.05
  4317.1 1690.84  4411.9 1678.76  4456.2 1673.24  4555.9 1668.88  4688.0 1669.13
  4811.6 1673.72  4887.1 1672.10  4972.3 1667.29  4986.9 1661.11  4987.4 1660.61
  5007.3 1661.11  5032.5 1661.54  5064.3 1669.03  5087.4 1684.11  5112.1 1708.97
  5117.8 1719.67  5142.3 1736.89  5160.6 1738.17  5203.4 1760.16  5246.2 1778.19
  5252.0 1782.61  5299.7 1800.96  5374.6 1833.65  5416.6 1847.98  5455.5 1856.55
#Mann=9,-1,0
  3615.5   0.035       0  3661.2    0.07       0  3685.1   0.035       0
  4122.3    0.07       0  4411.9     0.1       0  4555.9    0.07       0
  4887.1   0.035       0  4986.9    0.05       0  5007.3     0.1       0
Bank Sta=4986.9,5007.3
Exp/Cntr=0.3,0.1

Type RM Length L Ch R = 1,4486,566,566,566
BEGIN DESCRIPTION:
Palmer Creek 8.0
END DESCRIPTION:
XS GIS Cut Line= 3
      1922725.01     13874275.02      1922525.00     13873925.00
      1922275.01     13873475.01
#Sta/Elev= 30
  4596.9 1699.25  4638.6 1697.62  4691.5 1695.73  4741.3 1694.22  4766.1 1693.24
  4771.8 1691.01  4781.2 1689.99  4793.4 1692.78  4919.4 1690.68  4927.3 1688.38
  4933.1 1676.40  4948.9 1664.32  4954.7 1661.22  4970.5 1658.20  4981.8 1657.62
  4982.3 1657.12  5002.5 1657.62  5014.7 1658.54  5041.2 1660.81  5057.2 1663.62
  5073.2 1664.29  5103.0 1664.57  5148.7 1662.54  5219.7 1669.17  5257.4 1669.67
  5263.1 1670.17  5286.0 1678.17  5344.4 1681.94  5478.0 1682.24  5514.8 1683.89
#Mann=9,-1,0
  4596.9   0.035       0  4638.6    0.07       0  4691.5   0.035       0
  4741.3    0.07       0  4981.8    0.05       0  5002.5    0.07       0
  5014.7     0.1       0  5041.2    0.07       0  5478.0     0.1       0
Bank Sta=4981.8,5002.5
Exp/Cntr=0.3,0.1

Type RM Length L Ch R = 1,3920,558,558,558
BEGIN DESCRIPTION:
Palmer Creek 7.0
END DESCRIPTION:
XS GIS Cut Line= 3
      1923225.03     13873725.02      1922875.00     13873525.00
      1922075.02     13872725.02
#Sta/Elev= 30
  4597.1 1691.69  4648.2 1689.25  4685.7 1684.65  4744.7 1680.88  4839.0 1676.62
  4852.7 1674.82  4868.5 1665.99  4896.6 1657.38  4976.2 1652.46  4976.7 1651.96
  4997.0 1652.46  4997.4 1653.91  5035.6 1653.10  5056.8 1666.55  5071.0 1669.82
  5085.1 1671.53  5143.4 1672.73  5226.5 1677.06  5254.8 1676.67  5283.1 1679.03
  5523.5 1682.82  5602.7 1682.60  5672.0 1685.77  5735.6 1691.29  5877.1 1712.16
  5933.6 1726.36  5990.2 1744.48  6075.1 1773.69  6128.1 1798.11  6131.6 1798.11
#Mann=5,-1,0
  4597.1    0.07       0  4976.2    0.05       0  4997.0    0.07       0
  5143.4   0.035       0  5602.7     0.1       0
Bank Sta=4976.2,4997
Exp/Cntr=0.3,0.1

Type RM Length L Ch R = 1,3362,540,540,540
BEGIN DESCRIPTION:
Palmer Creek 6.0
END DESCRIPTION:
XS GIS Cut Line= 3
      1923425.00     13873475.00      1923225.00     13873125.00
      1922424.99     13872324.99
#Sta/Elev= 30
  4601.5 1691.92  4749.1 1685.86  4808.1 1678.24  4813.9 1674.88  4829.7 1677.80
  4835.4 1674.52  4851.3 1676.36  4857.0 1669.37  4872.9 1667.11  4878.6 1660.81
  4935.4 1652.53  5008.3 1649.77  5008.8 1649.27  5029.2 1649.77  5032.1 1649.88
  5047.0 1655.95  5167.2 1672.22  5230.9 1677.03  5437.3 1677.82  5473.9 1678.75
  5570.3 1679.20  5669.3 1682.88  5707.0 1686.76  5747.1 1690.55  5768.3 1695.73
  5810.7 1712.05  5853.1 1732.91  5895.6 1744.51  5994.6 1785.95  6136.0 1833.86
#Mann=9,-1,0
  4601.5    0.07       0  4935.4     0.1       0  5008.3    0.05       0
  5029.2     0.1       0  5032.1    0.07       0  5167.2   0.035       0
  5437.3     0.1       0  5473.9   0.035       0  5707.0     0.1       0
Bank Sta=5008.3,5029.2
Exp/Cntr=0.3,0.1

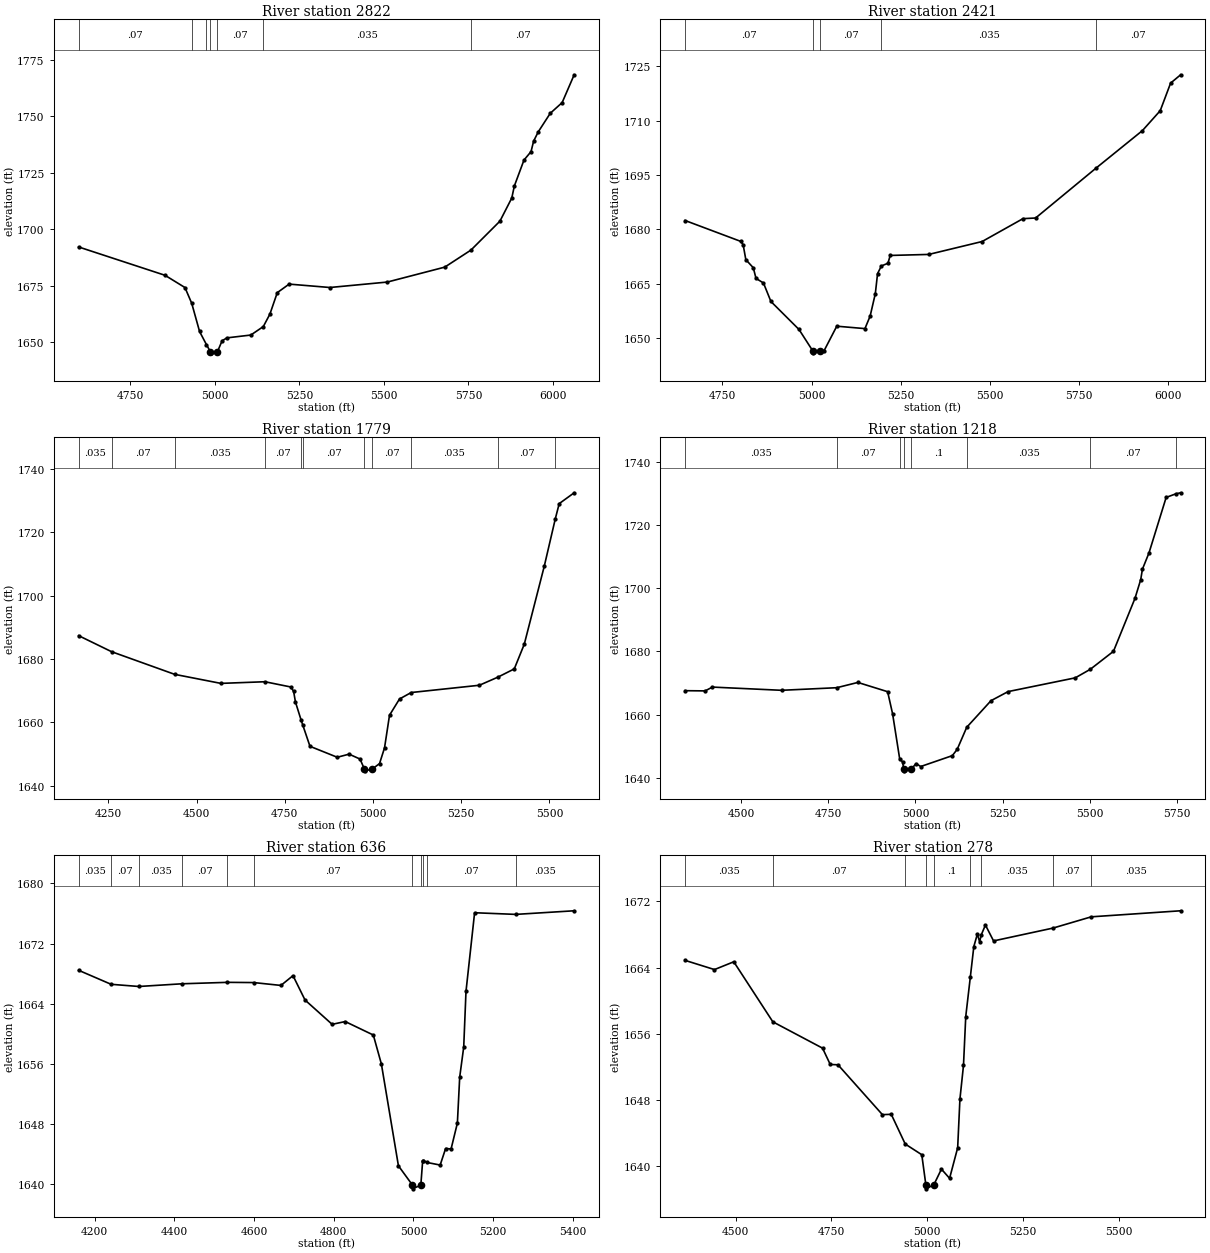
Type RM Length L Ch R = 1,2822,401,401,401
BEGIN DESCRIPTION:
Palmer Creek 5.0
END DESCRIPTION:
XS GIS Cut Line= 3
      1923875.01     13872925.01      1923525.00     13872725.00
      1922725.03     13872025.03
#Sta/Elev= 30
  4596.9 1692.14  4852.5 1679.61  4911.5 1674.19  4931.5 1667.22  4954.7 1654.75
  4974.9 1648.99  4986.7 1645.81  4987.2 1645.31  5007.6 1645.81  5021.4 1650.65
  5035.6 1651.93  5106.3 1653.18  5143.3 1656.93  5162.8 1662.44  5184.6 1671.93
  5219.7 1675.71  5340.3 1674.21  5510.2 1676.62  5680.1 1683.22  5757.6 1690.76
  5843.3 1703.55  5878.4 1713.79  5886.0 1719.10  5914.5 1730.58  5935.4 1734.32
  5943.0 1738.95  5956.7 1743.05  5992.3 1751.27  6027.4 1755.99  6063.0 1768.30
#Mann=7,-1,0
  4596.9    0.07       0  4931.5     0.1       0  4974.9    0.07       0
  4986.7    0.05       0  5007.6    0.07       0  5143.3   0.035       0
  5757.6    0.07       0
Bank Sta=4986.7,5007.6
Exp/Cntr=0.3,0.1

Type RM Length L Ch R = 1,2421,642,642,642
BEGIN DESCRIPTION:
Palmer Creek 4.0
END DESCRIPTION:
XS GIS Cut Line= 3
      1923974.97     13872624.97      1923671.00     13872357.12
      1923074.98     13871574.98
#Sta/Elev= 30
  4645.7 1682.42  4801.7 1676.65  4808.4 1675.71  4815.9 1671.60  4836.8 1669.37
  4844.4 1666.43  4865.3 1665.16  4886.2 1660.05  4964.9 1652.32  5003.7 1646.37
  5004.2 1645.87  5024.7 1646.37  5035.1 1646.45  5070.7 1653.23  5149.6 1652.56
  5164.2 1656.03  5178.7 1662.22  5185.0 1667.76  5195.7 1669.86  5214.1 1670.62
  5220.4 1672.77  5328.4 1673.05  5478.1 1676.62  5592.4 1682.93  5627.8 1683.11
  5797.4 1696.91  5927.1 1707.25  5977.0 1712.75  6006.1 1720.37  6034.2 1722.67
#Mann=5,-1,0
  4645.7    0.07       0  5003.7    0.05       0  5024.7    0.07       0
  5195.7   0.035       0  5797.4    0.07       0
Bank Sta=5003.7,5024.7
Exp/Cntr=0.3,0.1

Type RM Length L Ch R = 1,1779,561,561,561
BEGIN DESCRIPTION:
Palmer Creek 3.0
END DESCRIPTION:
XS GIS Cut Line= 4
      1924178.39     13872738.56      1924075.00     13872325.00
      1923975.00     13871925.00      1923574.99     13871524.99
#Sta/Elev= 30
  4165.8 1687.37  4259.2 1682.31  4438.0 1675.17  4568.9 1672.32  4693.7 1672.84
  4767.3 1671.18  4775.1 1669.78  4780.2 1666.47  4796.0 1660.85  4800.8 1659.25
  4821.4 1652.48  4898.7 1649.03  4932.2 1650.01  4963.2 1648.47  4975.9 1645.25
  4976.4 1644.75  4996.9 1645.25  5018.5 1647.03  5032.7 1652.01  5046.8 1662.28
  5075.1 1667.40  5108.3 1669.44  5301.4 1671.73  5353.6 1674.27  5400.4 1676.89
  5428.7 1684.67  5485.2 1709.19  5516.8 1724.28  5527.7 1728.99  5570.1 1732.41
#Mann=11,-1,0
  4165.8   0.035       0  4259.2    0.07       0  4438.0   0.035       0
  4693.7    0.07       0  4796.0     0.1       0  4800.8    0.07       0
  4975.9    0.05       0  4996.9    0.07       0  5108.3   0.035       0
  5353.6    0.07       0  5516.8   0.035       0
Bank Sta=4975.9,4996.9
Exp/Cntr=0.3,0.1

Type RM Length L Ch R = 1,1218,582,582,582
BEGIN DESCRIPTION:
Palmer Creek 2.0
END DESCRIPTION:
XS GIS Cut Line= 4
      1924812.13     13872078.41      1924657.92     13871900.81
      1924375.00     13871575.00      1923625.04     13871475.01
#Sta/Elev= 30
  4338.3 1667.58  4395.8 1667.51  4416.7 1668.72  4615.2 1667.70  4773.7 1668.52
  4834.5 1670.19  4920.0 1667.26  4934.3 1660.24  4954.8 1645.86  4962.8 1645.06
  4966.5 1642.68  4967.0 1642.18  4987.5 1642.68  5001.7 1644.48  5015.1 1643.55
  5105.9 1647.00  5119.8 1648.99  5147.2 1655.98  5216.9 1664.41  5266.0 1667.29
  5459.0 1671.65  5502.2 1674.36  5568.7 1680.06  5630.5 1696.85  5646.9 1702.76
  5651.9 1706.09  5670.8 1711.27  5720.0 1728.82  5748.2 1729.97  5761.6 1730.29
#Mann=8,-1,0
  4338.3   0.035       0  4773.7    0.07       0  4954.8     0.1       0
  4966.5    0.05       0  4987.5     0.1       0  5147.2   0.035       0
  5502.2    0.07       0  5748.2   0.035       0
Bank Sta=4966.5,4987.5
Exp/Cntr=0.3,0.1

Type RM Length L Ch R = 1,636,358,358,358
BEGIN DESCRIPTION:
Palmer Creek 1.0
END DESCRIPTION:
XS GIS Cut Line= 4
      1924879.20     13872008.60      1924825.00     13871575.00
      1924775.00     13871175.00      1924425.00     13870975.00
#Sta/Elev= 30
  4159.9 1668.44  4241.4 1666.58  4311.0 1666.29  4419.8 1666.65  4533.3 1666.84
  4599.3 1666.81  4667.4 1666.43  4697.7 1667.73  4727.9 1664.49  4795.9 1661.26
  4828.7 1661.63  4899.2 1659.84  4919.4 1656.00  4962.2 1642.46  4997.4 1639.90
  4997.9 1639.40  5018.4 1639.90  5023.0 1643.12  5024.8 1643.13  5033.5 1642.91
  5066.9 1642.56  5080.6 1644.76  5094.3 1644.70  5110.1 1648.14  5115.9 1654.24
  5126.0 1658.25  5131.7 1665.63  5153.3 1676.09  5256.4 1675.87  5403.1 1676.35
#Mann=11,-1,0
  4159.9   0.035       0  4241.4    0.07       0  4311.0   0.035       0
  4419.8    0.07       0  4533.3   0.035       0  4599.3    0.07       0
  4997.4    0.05       0  5018.4    0.07       0  5024.8     0.1       0
  5033.5    0.07       0  5256.4   0.035       0
Bank Sta=4997.4,5018.4
Exp/Cntr=0.3,0.1

Type RM Length L Ch R = 1,278,0,0,0
BEGIN DESCRIPTION:
Palmer Creek 0.0
END DESCRIPTION:
XS GIS Cut Line= 4
      1925252.02     13871501.06      1925195.29     13871050.06
      1924849.66     13870826.47      1924430.54     13870741.21
#Sta/Elev= 30
  4368.2 1664.88  4444.9 1663.77  4495.3 1664.71  4597.3 1657.46  4727.1 1654.28
  4747.2 1652.31  4767.4 1652.27  4883.4 1646.25  4906.5 1646.29  4943.0 1642.70
  4986.2 1641.41  4996.8 1637.79  4997.3 1637.29  5017.8 1637.79  5037.5 1639.67
  5058.8 1638.56  5079.9 1642.25  5085.8 1648.13  5095.1 1652.19  5101.0 1658.10
  5113.1 1662.92  5122.1 1666.55  5131.3 1668.05  5137.3 1667.12  5141.5 1667.96
  5152.4 1669.15  5173.6 1667.23  5328.8 1668.78  5428.7 1670.14  5662.1 1670.87
#Mann=9,-1,0
  4368.2   0.035       0  4597.3    0.07       0  4943.0     0.1       0
  4996.8    0.05       0  5017.8     0.1       0  5113.1    0.07       0
  5141.5   0.035       0  5328.8    0.07       0  5428.7   0.035       0
Bank Sta=4996.8,5017.8
Exp/Cntr=0.3,0.1

Chan Stop Cuts=-1