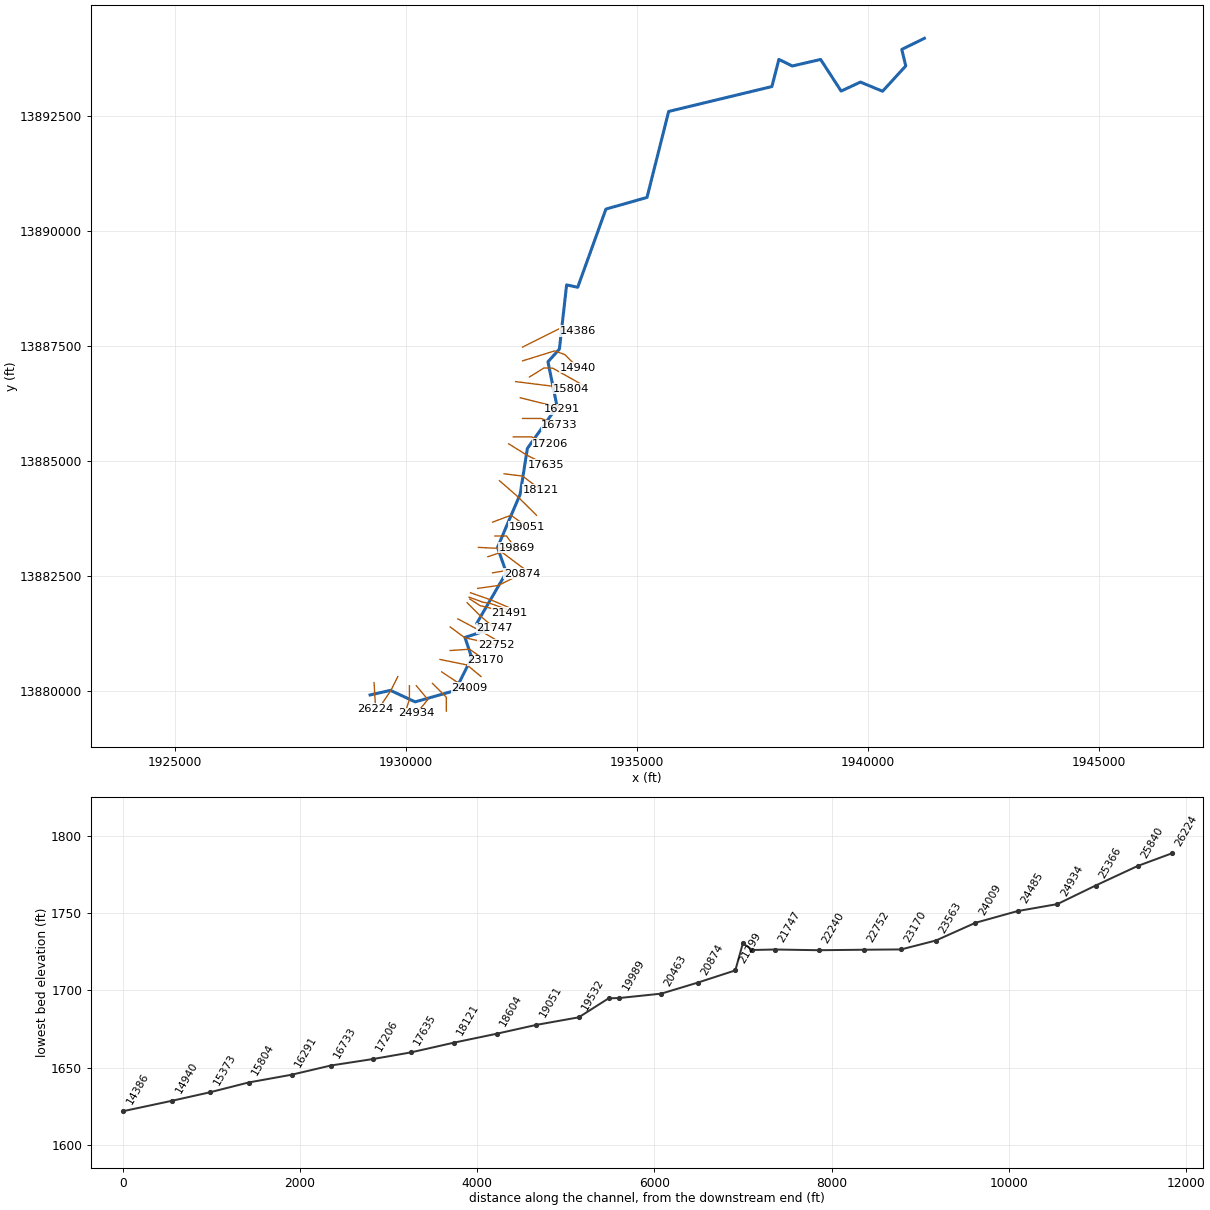
--- Pass Creek.prj (project) ---

Proj Title=Pass Creek Base Level Engineering
Current Plan=p01
Default Exp/Contr=0.3,0.1
English Units
Geom File=g01
Flow File=f01
Plan File=p01
BEGIN DESCRIPTION:
Pass Creek
END DESCRIPTION:

--- Pass Creek.p01 (plan) ---

Plan Title=Multiple Run
Short Identifier=Multiple
Geom File=g01
Flow File=f01
Subcritical Flow
K Sum by GR= 0
Std Step Tol= 0.01
Critical Tol= 0.01
Num of Std Step Trials= 20
Max Error Tol= 0.3
Flow Tol Ratio= 0.001
Split Flow NTrial= 30
Split Flow Tol= 0.02
Split Flow Ratio= 0.02
Log Output Level= 0
Friction Slope Method= 1
Unsteady Friction Slope Method= 2
Unsteady Bridges Friction Slope Method= 1
Parabolic Critical Depth
Global Vel Dist=  1 , 1 , 1
Global Log Level= 0
CheckData=True
Encroach Param= -1, 0, 0, 0
BEGIN DESCRIPTION:
Multiple Run
END DESCRIPTION:

--- Pass Creek.f01 (steady flow) ---

Flow Title=Multiple
Number of Profiles=7
Profile Names=10-year,25-year,50-year,1pct_min,100-year,1pct_plu,500-year
River Rch & RM= Pass Creek,Reach-1,26224
     795    1324    1818    1211    2417    4822    4205
River Rch & RM= Pass Creek,Reach-1,23563
    1580    2732    3846    2618    5223   10421    9503
River Rch & RM= Pass Creek,Reach-1,19051
    2010    3526    5011    3437    6857   13682   12687
River Rch & RM= Pass Creek,Reach-1,14194
    2300    4066    5807    4001    7982   15927   14908
River Rch & RM= Pass Creek,Reach-1,13916
    2822    5035    7234    5011    9998   19948   18875
River Rch & RM= Pass Creek,Reach-1,11188
    3051    5458    7855    5448   10870   21688   20577
River Rch & RM= Pass Creek,Reach-1,9329
    3391    6085    8776    6096   12163   24269   23101
River Rch & RM= Pass Creek,Reach-1,5596
    3532    6333    9127    6333   12636   25212   23947
Boundary for River Rch & Prof#=Pass Creek,Reach-1,1
Up Type=0
Dn Type=3
Dn Slope=0.005
Boundary for River Rch & Prof#=Pass Creek,Reach-1,2
Up Type=0
Dn Type=3
Dn Slope=0.005
Boundary for River Rch & Prof#=Pass Creek,Reach-1,3
Up Type=0
Dn Type=3
Dn Slope=0.005
Boundary for River Rch & Prof#=Pass Creek,Reach-1,4
Up Type=0
Dn Type=3
Dn Slope=0.005
Boundary for River Rch & Prof#=Pass Creek,Reach-1,5
Up Type=0
Dn Type=3
Dn Slope=0.005
Boundary for River Rch & Prof#=Pass Creek,Reach-1,6
Up Type=0
Dn Type=3
Dn Slope=0.005
Boundary for River Rch & Prof#=Pass Creek,Reach-1,7
Up Type=0
Dn Type=3
Dn Slope=0.005

--- Pass Creek.g01 (geometry) ---

Geom Title=Existing Conditions

River Reach=Pass Creek,Reach-1
Reach XY= 30
      1929225.00     13879925.00      1929664.51     13880024.06
      1930200.00     13879774.59      1931069.31     13880022.61
      1931423.92     13880735.54      1931277.99     13881173.60
      1931714.10     13881315.08      1931532.83     13881478.22
      1932172.95     13882580.86      1931982.84     13883128.23
      1932472.74     13884280.94      1932628.76     13885273.44
      1933273.02     13886180.67      1933074.96     13887155.02
      1933322.94     13887430.85      1933478.54     13888824.03
      1933719.17     13888772.13      1934329.80     13890469.38
      1935219.54     13890722.52      1935688.37     13892588.32
      1937923.53     13893128.54      1938074.75     13893718.02
      1938364.81     13893574.55      1938978.30     13893716.92
      1939422.57     13893030.40      1939840.19     13893225.53
      1940319.45     13893026.77      1940821.53     13893576.50
      1940735.43     13893934.79      1941225.00     13894175.00

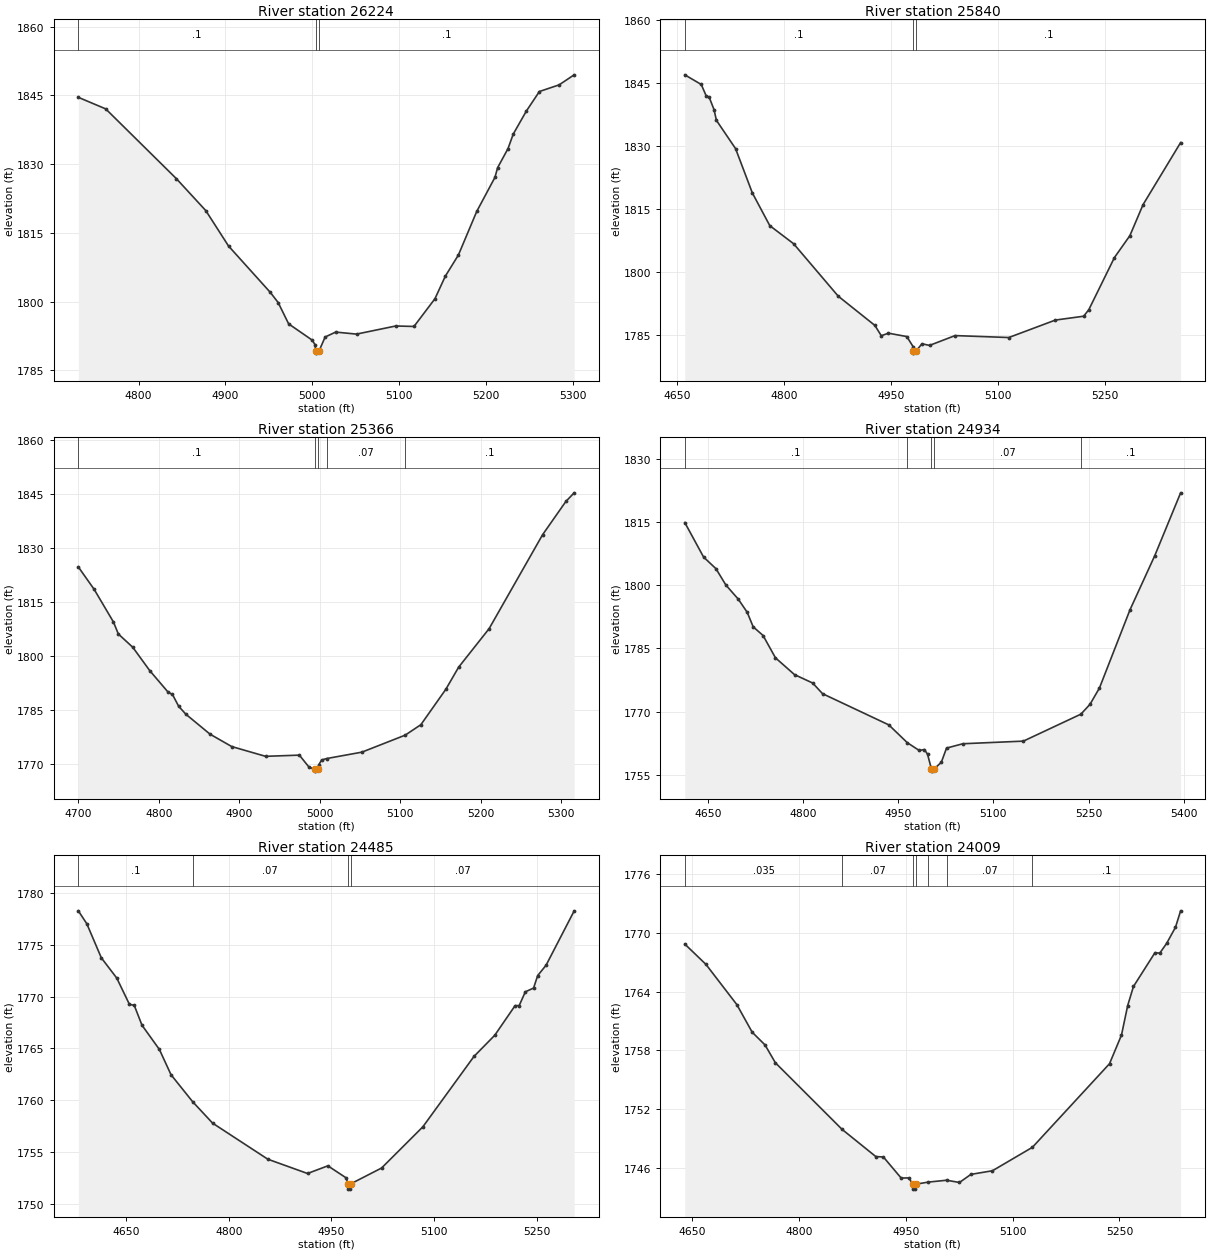
Type RM Length L Ch R = 1,26224,384,384,384
BEGIN DESCRIPTION:
Pass Creek 56.0
END DESCRIPTION:
XS GIS Cut Line= 2
      1929309.76     13880193.76      1929344.48     13879624.32
#Sta/Elev= 30
  4730.7 1844.57  4762.2 1842.05  4843.4 1826.85  4877.4 1819.85  4903.5 1812.14
  4951.6 1802.02  4960.6 1799.81  4972.7 1795.15  4999.7 1791.62  5003.1 1790.60
  5003.7 1789.27  5004.0 1788.77  5007.7 1789.27  5014.7 1792.29  5026.8 1793.36
  5050.8 1792.92  5095.9 1794.69  5116.9 1794.59  5141.0 1800.63  5153.0 1805.57
  5168.0 1810.17  5189.1 1819.68  5210.1 1827.13  5213.1 1829.21  5225.1 1833.39
  5231.1 1836.55  5246.2 1841.58  5261.2 1845.84  5283.9 1847.29  5301.2 1849.48
#Mann=3,-1,0
  4730.7     0.1       0  5003.7    0.05       0  5007.7     0.1       0
Bank Sta=5003.7,5007.7
Exp/Cntr=0.3,0.1

Type RM Length L Ch R = 1,25840,474,474,474
BEGIN DESCRIPTION:
Pass Creek 55.0
END DESCRIPTION:
XS GIS Cut Line= 3
      1929825.00     13880324.99      1929675.00     13880025.00
      1929474.98     13879724.96
#Sta/Elev= 30
  4660.7 1846.95  4683.8 1844.65  4690.5 1842.02  4695.0 1841.58  4701.7 1838.67
  4705.1 1836.10  4732.0 1829.35  4755.5 1818.80  4780.0 1811.00  4813.5 1806.68
  4876.1 1794.18  4927.5 1787.22  4936.5 1784.76  4946.6 1785.36  4972.3 1784.56
  4981.2 1782.15  4981.4 1781.11  4981.7 1780.61  4985.4 1781.11  4993.6 1782.84
  5004.2 1782.45  5040.1 1784.79  5115.5 1784.33  5180.9 1788.49  5220.6 1789.41
  5227.8 1790.96  5263.8 1803.40  5285.5 1808.62  5304.0 1816.02  5356.7 1830.80
#Mann=3,-1,0
  4660.7     0.1       0  4981.4    0.05       0  4985.4     0.1       0
Bank Sta=4981.4,4985.4
Exp/Cntr=0.3,0.1

Type RM Length L Ch R = 1,25366,432,432,432
BEGIN DESCRIPTION:
Pass Creek 54.0
END DESCRIPTION:
XS GIS Cut Line= 3
      1930075.00     13880124.98      1930075.00     13879825.00
      1929975.00     13879525.01
#Sta/Elev= 30
  4700.0 1824.77  4719.7 1818.52  4743.7 1809.43  4749.7 1806.12  4767.7 1802.41
  4788.7 1795.94  4811.5 1789.95  4817.0 1789.28  4824.7 1786.00  4833.7 1783.78
  4863.7 1778.24  4890.7 1774.79  4932.7 1772.08  4974.7 1772.41  4986.7 1769.07
  4993.7 1768.46  4994.0 1767.96  4997.7 1768.46  4998.7 1769.70  5002.4 1771.06
  5008.6 1771.46  5052.4 1773.24  5106.2 1777.97  5125.7 1780.88  5156.8 1790.76
  5172.6 1796.87  5210.5 1807.60  5277.0 1833.75  5305.9 1842.99  5316.2 1845.39
#Mann=5,-1,0
  4700.0     0.1       0  4993.7    0.05       0  4997.7     0.1       0
  5008.6    0.07       0  5106.2     0.1       0
Bank Sta=4993.7,4997.7
Exp/Cntr=0.3,0.1

Type RM Length L Ch R = 1,24934,449,449,449
BEGIN DESCRIPTION:
Pass Creek 53.0
END DESCRIPTION:
XS GIS Cut Line= 3
      1930225.03     13880124.96      1930475.00     13879825.00
      1930224.98     13879524.98
#Sta/Elev= 30
  4613.9 1814.83  4643.5 1806.65  4663.0 1803.89  4678.6 1800.02  4698.1 1796.68
  4712.2 1793.56  4721.6 1790.12  4737.2 1788.06  4756.7 1782.77  4786.7 1778.79
  4815.3 1776.80  4830.9 1774.27  4935.2 1766.88  4964.3 1762.67  4983.2 1760.81
  4991.2 1761.04  4996.2 1759.95  5002.4 1756.42  5002.6 1755.92  5006.4 1756.42
  5017.9 1758.00  5026.2 1761.38  5051.9 1762.41  5147.2 1763.03  5237.8 1769.42
  5252.2 1771.76  5267.1 1775.64  5315.2 1794.17  5354.2 1806.99  5394.9 1821.87
#Mann=5,-1,0
  4613.9     0.1       0  4964.3    0.07       0  5002.4    0.05       0
  5006.4    0.07       0  5237.8     0.1       0
Bank Sta=5002.4,5006.4
Exp/Cntr=0.3,0.1

Type RM Length L Ch R = 1,24485,476,476,476
BEGIN DESCRIPTION:
Pass Creek 52.0
END DESCRIPTION:
XS GIS Cut Line= 3
      1930575.00     13880175.00      1930875.00     13879875.00
      1930875.00     13879574.96
#Sta/Elev= 30
  4580.2 1778.28  4592.6 1777.03  4613.8 1773.74  4636.4 1771.78  4654.8 1769.25
  4661.9 1769.15  4673.2 1767.23  4698.6 1764.89  4715.6 1762.45  4747.1 1759.85
  4776.4 1757.77  4857.0 1754.29  4915.0 1752.91  4944.7 1753.65  4971.6 1752.48
  4973.8 1751.90  4974.1 1751.40  4977.6 1751.40  4977.8 1751.90  5023.2 1753.44
  5083.5 1757.42  5158.2 1764.22  5188.5 1766.26  5218.2 1769.12  5224.2 1769.13
  5233.2 1770.46  5245.2 1770.82  5251.2 1772.02  5263.5 1773.03  5304.5 1778.27
#Mann=4,-1,0
  4580.2     0.1       0  4747.1    0.07       0  4973.8    0.05       0
  4977.8    0.07       0
Bank Sta=4973.8,4977.8
Exp/Cntr=0.3,0.1

Type RM Length L Ch R = 1,24009,446,446,446
BEGIN DESCRIPTION:
Pass Creek 51.0
END DESCRIPTION:
XS GIS Cut Line= 3
      1930775.03     13880424.98      1931075.00     13880225.00
      1931374.97     13880075.02
#Sta/Elev= 30
  4640.0 1768.87  4669.7 1766.79  4713.0 1762.68  4734.6 1759.85  4752.6 1758.55
  4767.1 1756.73  4860.8 1749.91  4908.1 1747.13  4918.7 1747.09  4943.7 1744.93
  4954.6 1744.95  4959.8 1744.30  4960.0 1743.80  4963.5 1743.80  4963.8 1744.30
  4981.8 1744.52  5007.5 1744.71  5025.5 1744.48  5041.6 1745.31  5071.8 1745.68
  5127.9 1748.08  5236.1 1756.63  5252.9 1759.56  5261.6 1762.58  5269.7 1764.53
  5299.9 1767.99  5306.6 1767.94  5316.2 1768.93  5328.7 1770.59  5335.9 1772.27
#Mann=7,-1,0
  4640.0   0.035       0  4860.8    0.07       0  4959.8    0.05       0
  4963.8    0.07       0  4981.8     0.1       0  5007.5    0.07       0
  5127.9     0.1       0
Bank Sta=4959.8,4963.8
Exp/Cntr=0.3,0.1

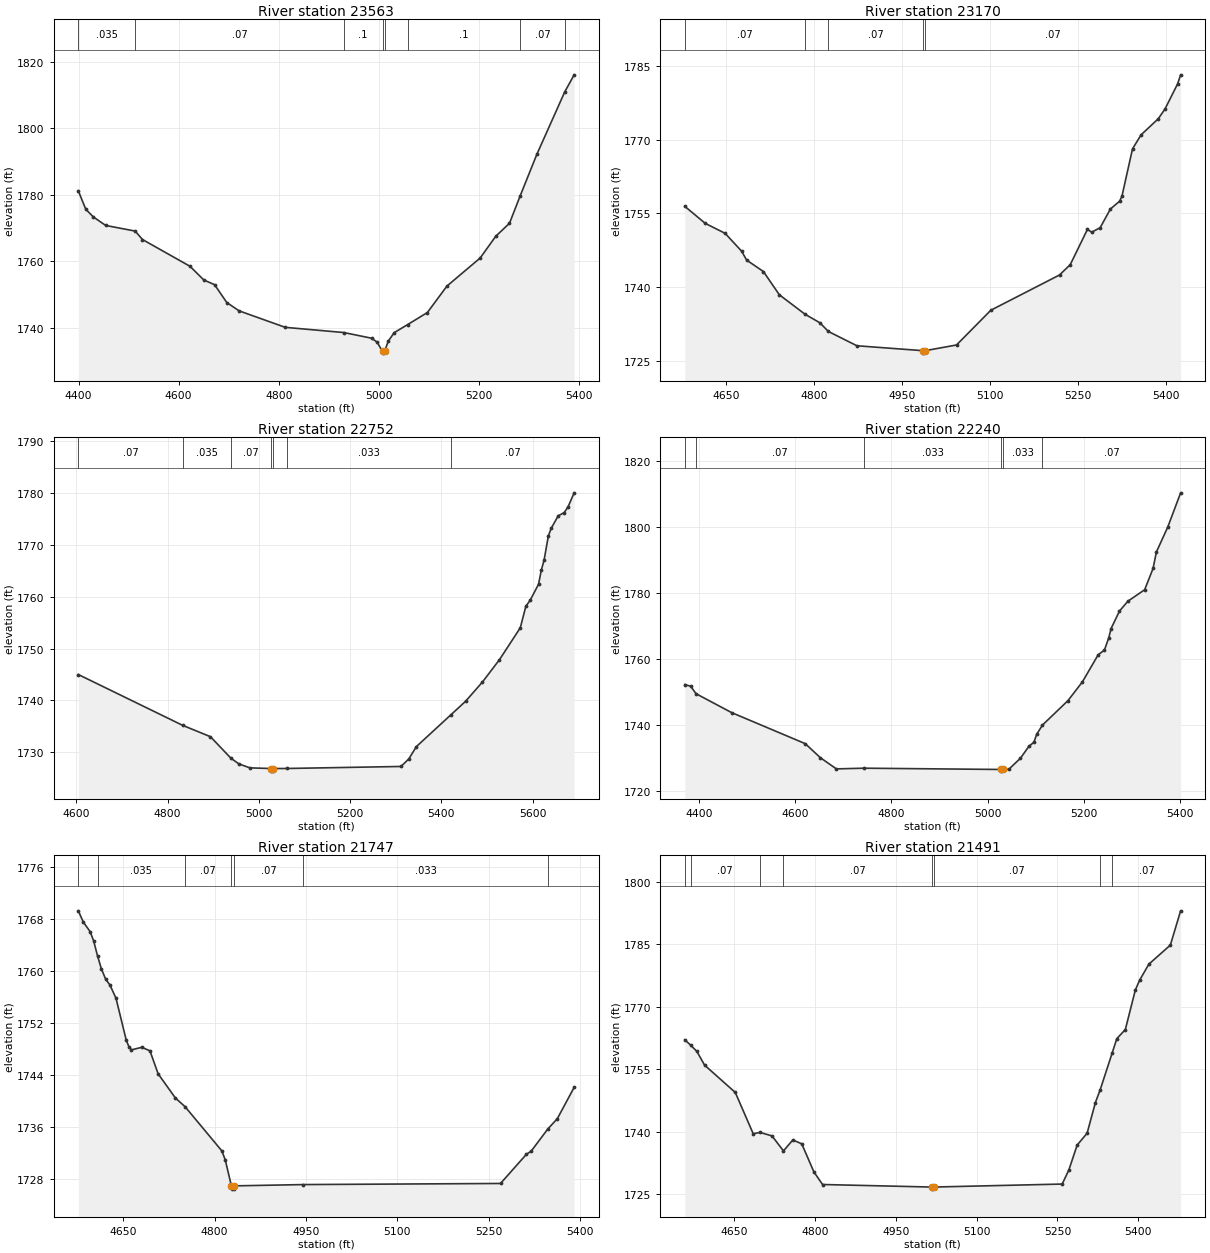
Type RM Length L Ch R = 1,23563,393,393,393
BEGIN DESCRIPTION:
Pass Creek 50.0
END DESCRIPTION:
XS GIS Cut Line= 3
      1930737.18     13880696.21      1931325.00     13880575.00
      1931625.00     13880325.00
#Sta/Elev= 30
  4399.6 1781.18  4414.5 1775.64  4429.8 1773.31  4454.3 1770.77  4513.1 1769.08
  4527.8 1766.53  4622.8 1758.47  4650.3 1754.35  4671.8 1752.94  4696.2 1747.57
  4720.8 1745.06  4813.1 1740.09  4930.0 1738.53  4985.6 1736.82  4996.5 1735.65
  5007.4 1732.83  5007.6 1732.33  5011.4 1732.83  5019.0 1735.97  5030.7 1738.49
  5057.8 1740.94  5097.1 1744.56  5136.1 1752.52  5202.5 1760.97  5233.8 1767.54
  5261.1 1771.43  5282.1 1779.55  5315.8 1792.20  5371.5 1810.99  5390.3 1816.12
#Mann=8,-1,0
  4399.6   0.035       0  4513.1    0.07       0  4930.0     0.1       0
  5007.4    0.05       0  5011.4     0.1       0  5057.8     0.1       0
  5282.1    0.07       0  5371.5     0.1       0
Bank Sta=5007.4,5011.4
Exp/Cntr=0.3,0.1

Type RM Length L Ch R = 1,23170,418,418,418
BEGIN DESCRIPTION:
Pass Creek 49.0
END DESCRIPTION:
XS GIS Cut Line= 3
      1930957.07     13880888.83      1931378.25     13880916.89
      1931725.00     13880675.00
#Sta/Elev= 30
  4580.0 1756.46  4614.8 1752.99  4648.7 1750.96  4676.9 1747.31  4685.3 1745.51
  4714.0 1743.17  4741.0 1738.45  4784.8 1734.48  4810.2 1732.73  4824.7 1730.96
  4873.3 1728.05  4985.6 1727.05  4985.8 1726.55  4989.6 1727.05  5043.0 1728.21
  5101.5 1735.29  5218.5 1742.47  5236.8 1744.57  5266.1 1751.76  5273.4 1751.19
  5287.8 1752.11  5305.3 1755.92  5321.0 1757.51  5324.9 1758.52  5342.9 1768.16
  5357.5 1771.02  5386.8 1774.30  5398.3 1776.29  5419.7 1781.39  5424.9 1783.25
#Mann=5,-1,0
  4580.0    0.07       0  4784.8   0.035       0  4824.7    0.07       0
  4985.6    0.05       0  4989.6    0.07       0
Bank Sta=4985.6,4989.6
Exp/Cntr=0.3,0.1

Type RM Length L Ch R = 1,22752,512,512,512
BEGIN DESCRIPTION:
Pass Creek 48.0
END DESCRIPTION:
XS GIS Cut Line= 3
      1930957.21     13881401.13      1931270.40     13881168.61
      1931949.90     13881013.29
#Sta/Elev= 30
  4604.1 1745.00  4832.8 1735.19  4893.7 1733.00  4938.6 1728.85  4956.2 1727.74
  4980.4 1726.98  5026.7 1726.85  5027.0 1726.35  5030.5 1726.35  5030.7 1726.85
  5060.7 1726.86  5311.5 1727.25  5328.7 1728.71  5345.3 1731.09  5420.4 1737.18
  5453.1 1739.83  5490.0 1743.54  5527.4 1747.86  5573.1 1754.02  5585.4 1758.21
  5594.6 1759.31  5613.1 1762.43  5619.2 1765.15  5625.4 1767.15  5634.6 1771.74
  5640.8 1773.21  5656.2 1775.64  5669.4 1776.27  5677.7 1777.35  5691.2 1780.08
#Mann=7,-1,0
  4604.1    0.07       0  4832.8   0.035       0  4938.6    0.07       0
  5026.7    0.05       0  5030.7    0.07       0  5060.7   0.033       0
  5420.4    0.07       0
Bank Sta=5026.7,5030.7
Exp/Cntr=0.3,0.1

Type RM Length L Ch R = 1,22240,493,493,493
BEGIN DESCRIPTION:
Pass Creek 47.0
END DESCRIPTION:
XS GIS Cut Line= 3
      1931125.01     13881575.00      1931683.35     13881277.25
      1932025.00     13881075.00
#Sta/Elev= 30
  4371.0 1752.31  4383.2 1751.79  4394.3 1749.53  4468.2 1743.80  4621.2 1734.37
  4652.6 1730.11  4685.8 1726.72  4743.5 1726.93  5027.8 1726.54  5028.1 1726.04
  5031.8 1726.54  5043.7 1726.57  5068.2 1729.96  5085.6 1733.55  5096.0 1734.79
  5101.9 1737.22  5113.9 1740.02  5166.7 1747.41  5196.8 1753.11  5229.6 1761.35
  5242.5 1762.75  5251.5 1766.46  5256.4 1769.31  5273.8 1774.60  5291.3 1777.59
  5326.1 1781.07  5343.6 1787.54  5350.5 1792.53  5374.2 1800.12  5400.8 1810.47
#Mann=6,-1,0
  4371.0   0.035       0  4394.3    0.07       0  4743.5   0.033       0
  5027.8   0.033       0  5031.8   0.033       0  5113.9    0.07       0
Bank Sta=5027.8,5031.8
Exp/Cntr=0.3,0.1

Type RM Length L Ch R = 1,21747,256,256,256
BEGIN DESCRIPTION:
Pass Creek 46.0
END DESCRIPTION:
XS GIS Cut Line= 3
      1931325.02     13881924.98      1931625.00     13881625.00
      1931924.97     13881375.03
#Sta/Elev= 30
  4576.0 1769.28  4584.1 1767.56  4595.4 1766.08  4601.1 1764.68  4607.5 1762.37
  4613.8 1760.38  4620.9 1758.77  4627.9 1757.88  4637.9 1755.84  4654.8 1749.37
  4659.1 1748.40  4663.3 1747.91  4680.3 1748.30  4693.7 1747.76  4707.1 1744.23
  4735.4 1740.52  4751.5 1739.16  4811.8 1732.38  4817.4 1731.00  4827.5 1727.00
  4827.7 1726.50  4831.2 1726.50  4831.5 1727.00  4945.9 1727.20  5269.7 1727.37
  5312.3 1731.86  5320.1 1732.34  5347.3 1735.73  5363.1 1737.34  5390.7 1742.15
#Mann=7,-1,0
  4576.0    0.07       0  4607.5   0.035       0  4751.5    0.07       0
  4827.5   0.033       0  4831.5    0.07       0  4945.9   0.033       0
  5347.3    0.07       0
Bank Sta=4827.5,4831.5
Exp/Cntr=0.3,0.1

Type RM Length L Ch R = 1,21491,107,107,107
BEGIN DESCRIPTION:
Mapping XS 7169eeb5
END DESCRIPTION:
XS GIS Cut Line= 3
      1931380.97     13882008.22      1931607.02     13881861.98
      1932240.59     13881709.03
#Sta/Elev= 30
  4557.9 1762.07  4568.5 1760.80  4580.3 1759.28  4594.6 1755.98  4651.7 1749.41
  4685.0 1739.48  4697.4 1739.81  4719.9 1738.97  4741.2 1735.36  4758.5 1737.99
  4775.1 1737.07  4797.8 1730.29  4813.8 1727.29  5016.2 1726.68  5016.4 1726.18
  5020.2 1726.68  5258.9 1727.40  5271.3 1730.79  5286.7 1736.76  5305.2 1739.62
  5320.6 1746.98  5329.6 1750.09  5352.0 1758.99  5360.4 1762.34  5376.2 1764.52
  5394.7 1773.99  5402.6 1776.35  5420.0 1780.25  5459.8 1784.81  5478.9 1793.05
#Mann=8,-1,0
  4557.9   0.035       0  4568.5    0.07       0  4697.4   0.035       0
  4741.2    0.07       0  5016.2    0.05       0  5020.2    0.07       0
  5329.6   0.035       0  5352.0    0.07       0
Bank Sta=5016.2,5020.2
Exp/Cntr=0.3,0.1

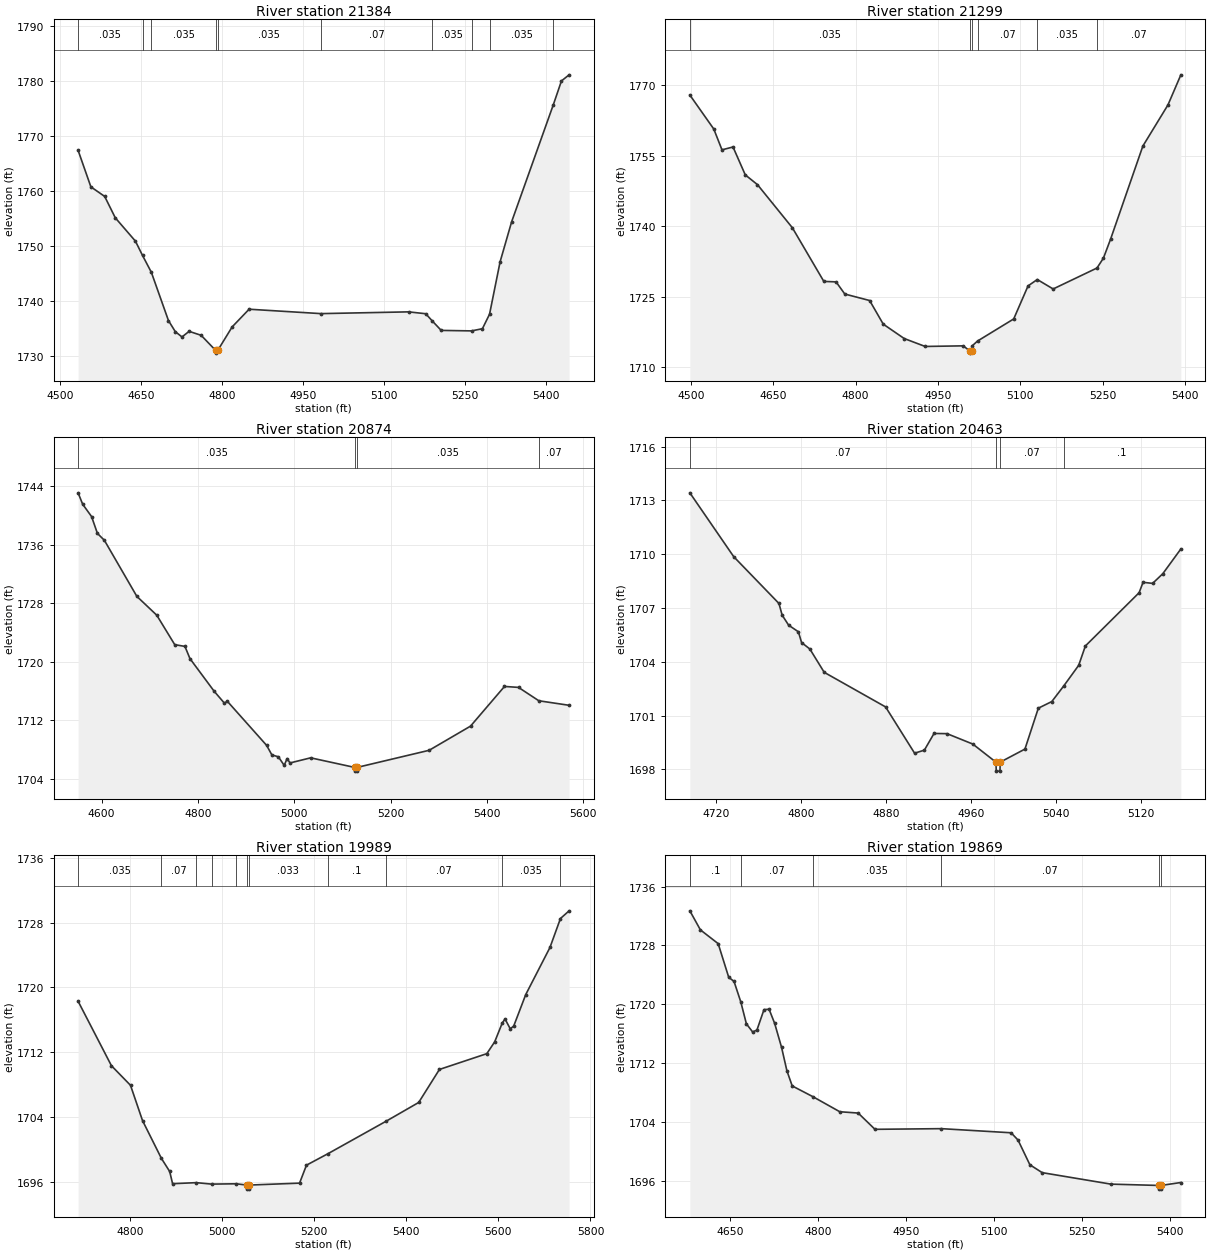
Type RM Length L Ch R = 1,21384,85,85,85
BEGIN DESCRIPTION:
Pass Creek 45.1
END DESCRIPTION:
XS GIS Cut Line= 4
      1931368.45     13882046.29      1931665.73     13881937.79
      1931817.64     13881913.92      1932232.12     13881766.35
#Sta/Elev= 30
  4533.3 1767.36  4557.0 1760.72  4582.6 1758.98  4602.2 1755.10  4639.6 1750.85
  4652.7 1748.26  4669.1 1745.19  4700.8 1736.42  4713.5 1734.40  4725.9 1733.44
  4739.1 1734.46  4761.4 1733.74  4788.2 1731.00  4788.4 1730.50  4792.2 1731.00
  4818.9 1735.27  4850.3 1738.48  4983.5 1737.68  5145.9 1738.00  5177.7 1737.66
  5190.2 1736.31  5206.4 1734.63  5262.6 1734.54  5282.8 1734.94  5296.0 1737.57
  5315.6 1747.11  5337.0 1754.39  5414.3 1775.66  5429.3 1779.97  5443.5 1781.08
#Mann=10,-1,0
  4533.3   0.035       0  4652.7    0.07       0  4669.1   0.035       0
  4788.2    0.05       0  4792.2   0.035       0  4983.5    0.07       0
  5190.2   0.035       0  5262.6    0.07       0  5296.0   0.035       0
  5414.3    0.07       0
Bank Sta=4788.2,4792.2
Exp/Cntr=0.3,0.1

Type RM Length L Ch R = 1,21299,425,425,425
BEGIN DESCRIPTION:
Pass Creek 45.0
END DESCRIPTION:
XS GIS Cut Line= 3
      1931397.59     13882142.69      1931875.00     13881975.00
      1932231.31     13881821.69
#Sta/Elev= 30
  4498.3 1767.92  4541.9 1760.68  4556.8 1756.25  4576.9 1756.86  4599.2 1750.92
  4621.4 1748.84  4685.0 1739.65  4742.2 1728.24  4764.5 1728.14  4780.4 1725.55
  4825.6 1724.17  4850.4 1719.14  4888.5 1716.08  4926.7 1714.39  4996.1 1714.52
  5007.5 1713.47  5007.7 1712.97  5011.5 1713.47  5012.7 1714.56  5022.0 1715.54
  5087.9 1720.25  5114.0 1727.28  5130.8 1728.64  5159.7 1726.63  5239.5 1731.09
  5251.2 1733.19  5264.3 1737.25  5323.0 1757.05  5368.7 1765.81  5392.2 1772.22
#Mann=6,-1,0
  4498.3   0.035       0  5007.5   0.035       0  5011.5   0.035       0
  5022.0    0.07       0  5130.8   0.035       0  5239.5    0.07       0
Bank Sta=5007.5,5011.5
Exp/Cntr=0.3,0.1

Type RM Length L Ch R = 1,20874,411,411,411
BEGIN DESCRIPTION:
Pass Creek 44.0
END DESCRIPTION:
XS GIS Cut Line= 3
      1931555.01     13882237.26      1931997.76     13882300.20
      1932509.82     13882556.23
#Sta/Elev= 30
  4551.2 1743.12  4560.7 1741.56  4579.2 1739.87  4591.3 1737.57  4605.8 1736.62
  4673.2 1728.95  4714.6 1726.37  4751.9 1722.34  4773.1 1722.10  4783.5 1720.43
  4833.8 1715.96  4855.2 1714.32  4861.0 1714.60  4942.8 1708.55  4953.6 1707.25
  4967.1 1706.99  4979.2 1705.82  4985.3 1706.75  4991.3 1706.15  5034.2 1706.85
  5126.1 1705.53  5126.3 1705.03  5129.8 1705.03  5130.1 1705.53  5280.2 1707.88
  5366.2 1711.19  5436.7 1716.62  5465.8 1716.49  5508.0 1714.66  5570.9 1714.04
#Mann=4,-1,0
  4551.2   0.035       0  5126.1   0.035       0  5130.1   0.035       0
  5508.0    0.07       0
Bank Sta=5126.1,5130.1
Exp/Cntr=0.3,0.1

Type RM Length L Ch R = 1,20463,474,474,474
BEGIN DESCRIPTION:
Pass Creek 43.0
END DESCRIPTION:
XS GIS Cut Line= 3
      1931874.98     13882575.00      1932175.00     13882625.00
      1932325.03     13882574.99
#Sta/Elev= 30
  4695.3 1713.42  4736.6 1709.86  4779.2 1707.25  4782.2 1706.60  4788.3 1706.04
  4797.5 1705.67  4800.5 1705.07  4808.3 1704.71  4821.8 1703.41  4879.6 1701.48
  4906.9 1698.90  4916.1 1699.07  4925.2 1700.00  4937.4 1699.99  4961.7 1699.41
  4983.5 1698.40  4983.8 1697.90  4987.3 1697.90  4987.5 1698.40  5010.8 1699.13
  5023.4 1701.41  5036.1 1701.78  5047.2 1702.64  5061.4 1703.80  5067.7 1704.88
  5118.3 1707.85  5122.0 1708.43  5131.0 1708.37  5140.6 1708.91  5157.6 1710.29
#Mann=4,-1,0
  4695.3    0.07       0  4983.5    0.05       0  4987.5    0.07       0
  5047.2     0.1       0
Bank Sta=4983.5,4987.5
Exp/Cntr=0.3,0.1

Type RM Length L Ch R = 1,19989,120,120,120
BEGIN DESCRIPTION:
Pass Creek 42.0
END DESCRIPTION:
XS GIS Cut Line= 3
      1931775.04     13882925.01      1932075.00     13883025.00
      1932675.01     13882574.99
#Sta/Elev= 30
  4687.4 1718.28  4759.8 1710.31  4801.2 1707.89  4827.3 1703.53  4868.3 1698.86
  4886.3 1697.24  4892.6 1695.73  4944.1 1695.86  4977.4 1695.68  5030.8 1695.72
  5053.8 1695.56  5054.0 1695.06  5057.5 1695.06  5057.8 1695.56  5168.3 1695.80
  5183.3 1698.02  5230.0 1699.44  5356.2 1703.45  5427.0 1705.77  5472.0 1709.85
  5574.9 1711.80  5592.0 1713.26  5608.6 1715.61  5614.5 1716.08  5625.8 1714.87
  5633.3 1715.21  5659.5 1719.11  5712.0 1724.92  5734.8 1728.50  5753.6 1729.45
#Mann=11,-1,0
  4687.4   0.035       0  4868.3    0.07       0  4944.1   0.035       0
  4977.4    0.07       0  5030.8   0.033       0  5053.8    0.05       0
  5057.8   0.033       0  5230.0     0.1       0  5356.2    0.07       0
  5608.6   0.035       0  5734.8   0.063       0
Bank Sta=5053.8,5057.8
Exp/Cntr=0.3,0.1

Type RM Length L Ch R = 1,19869,337,337,337
BEGIN DESCRIPTION:
Mapping XS 897321b5
END DESCRIPTION:
XS GIS Cut Line= 3
      1931570.51     13883127.38      1931919.64     13883109.66
      1932407.08     13883118.45
#Sta/Elev= 30
  4580.9 1732.70  4598.9 1730.11  4629.2 1728.24  4647.2 1723.66  4656.2 1723.11
  4667.8 1720.31  4677.3 1717.34  4688.0 1716.23  4695.3 1716.50  4707.3 1719.27
  4716.0 1719.32  4725.5 1717.40  4737.3 1714.13  4746.4 1710.95  4755.4 1708.90
  4790.6 1707.44  4836.5 1705.39  4867.9 1705.21  4896.5 1703.00  5009.8 1703.09
  5128.6 1702.53  5140.4 1701.54  5160.6 1698.18  5181.6 1697.11  5298.7 1695.55
  5380.1 1695.37  5380.4 1694.87  5383.9 1694.87  5384.1 1695.37  5418.0 1695.77
#Mann=6,-1,0
  4580.9     0.1       0  4667.8    0.07       0  4790.6   0.035       0
  5009.8    0.07       0  5380.1   0.035       0  5384.1    0.07       0
Bank Sta=5380.1,5384.1
Exp/Cntr=0.3,0.1

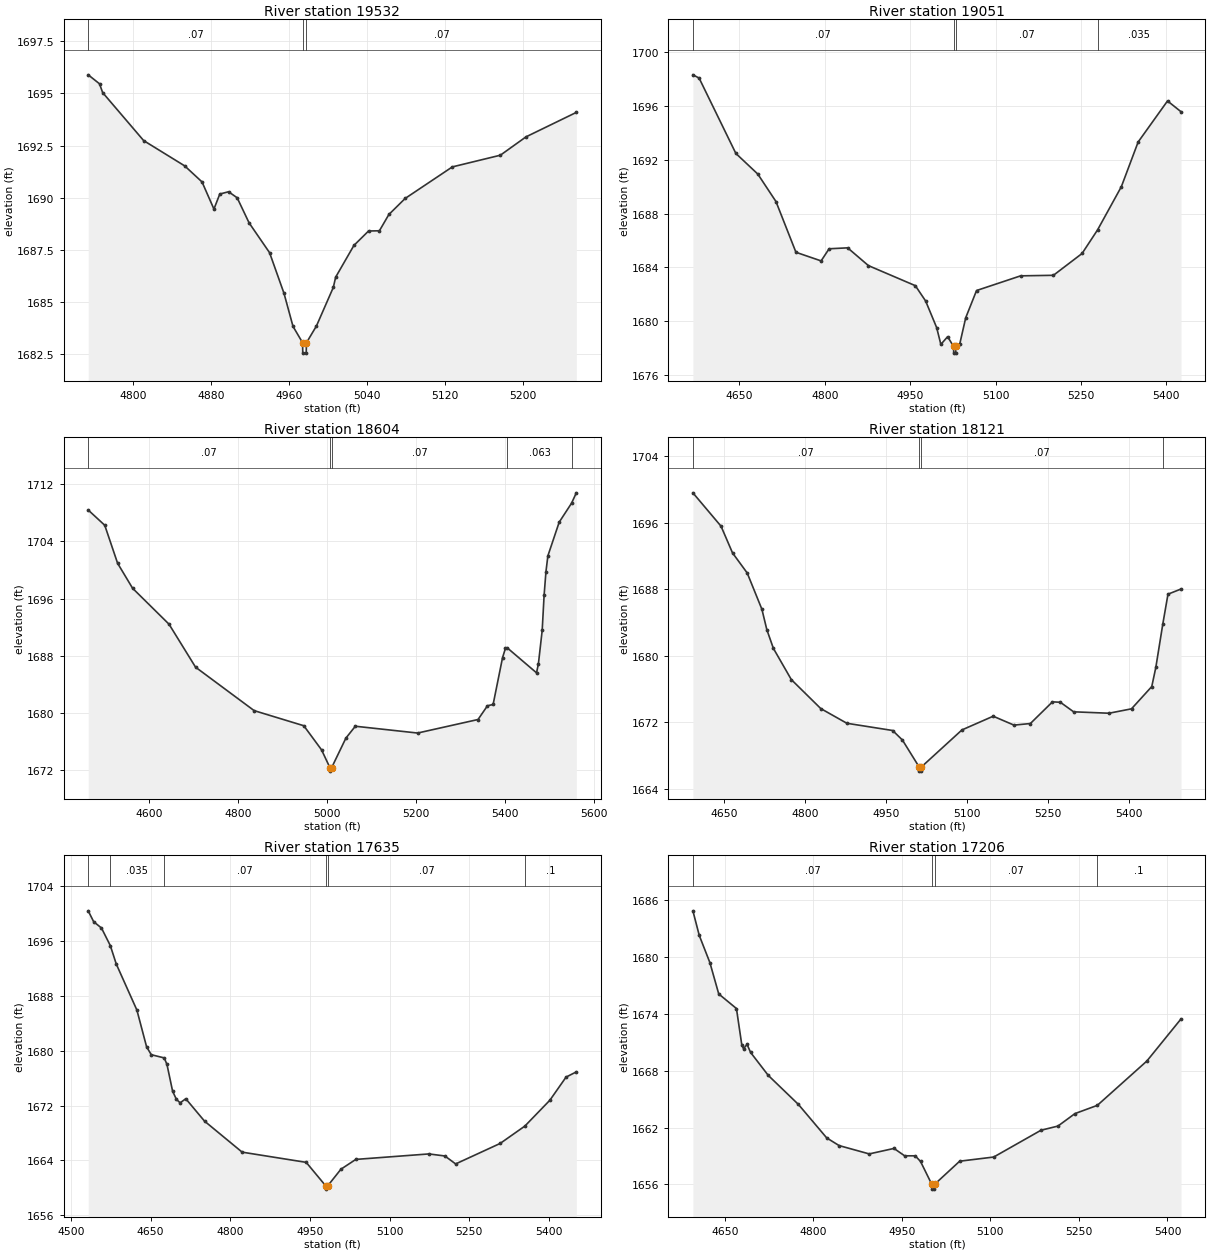
Type RM Length L Ch R = 1,19532,481,481,481
BEGIN DESCRIPTION:
Pass Creek 41.0
END DESCRIPTION:
XS GIS Cut Line= 3
      1931924.96     13883375.00      1932175.00     13883375.00
      1932324.98     13883175.03
#Sta/Elev= 30
  4754.3 1695.89  4765.9 1695.46  4769.1 1695.04  4811.1 1692.74  4853.1 1691.53
  4870.9 1690.76  4883.1 1689.46  4889.1 1690.18  4898.1 1690.29  4906.9 1690.00
  4919.1 1688.80  4940.1 1687.37  4954.9 1685.42  4964.1 1683.84  4973.9 1683.06
  4974.1 1682.56  4977.6 1682.56  4977.9 1683.06  4988.1 1683.86  5005.4 1685.71
  5007.8 1686.20  5026.5 1687.72  5041.5 1688.41  5052.6 1688.42  5062.3 1689.20
  5079.0 1689.97  5127.3 1691.48  5176.5 1692.04  5202.8 1692.92  5254.3 1694.09
#Mann=3,-1,0
  4754.3    0.07       0  4973.9    0.05       0  4977.9    0.07       0
Bank Sta=4973.9,4977.9
Exp/Cntr=0.3,0.1

Type RM Length L Ch R = 1,19051,447,447,447
BEGIN DESCRIPTION:
Pass Creek 40.0
END DESCRIPTION:
XS GIS Cut Line= 3
      1931875.01     13883675.01      1932275.00     13883825.00
      1932625.00     13883575.00
#Sta/Elev= 30
  4568.5 1698.30  4579.4 1698.06  4644.0 1692.46  4682.5 1690.93  4714.4 1688.89
  4749.5 1685.12  4793.7 1684.48  4807.7 1685.38  4840.3 1685.45  4876.8 1684.13
  4959.2 1682.64  4977.3 1681.50  4996.6 1679.53  5004.0 1678.28  5015.9 1678.85
  5026.3 1678.13  5026.6 1677.63  5030.1 1677.63  5030.4 1678.13  5037.2 1678.31
  5047.7 1680.26  5066.7 1682.28  5144.1 1683.37  5201.7 1683.41  5252.0 1685.03
  5279.2 1686.78  5321.0 1689.99  5350.5 1693.31  5402.1 1696.36  5425.8 1695.56
#Mann=4,-1,0
  4568.5    0.07       0  5026.3    0.05       0  5030.4    0.07       0
  5279.2   0.035       0
Bank Sta=5026.3,5030.4
Exp/Cntr=0.3,0.1

Type RM Length L Ch R = 1,18604,483,483,483
BEGIN DESCRIPTION:
Pass Creek 39.0
END DESCRIPTION:
XS GIS Cut Line= 3
      1932025.03     13884574.97      1932425.00     13884225.00
      1932824.97     13883825.03
#Sta/Elev= 30
  4463.9 1708.37  4501.1 1706.24  4530.0 1700.93  4563.7 1697.44  4645.6 1692.42
  4705.2 1686.42  4836.9 1680.35  4948.5 1678.24  4988.4 1674.87  5007.1 1672.40
  5007.4 1671.90  5011.2 1672.40  5043.1 1676.51  5064.3 1678.17  5204.3 1677.22
  5340.1 1679.11  5361.3 1681.03  5374.0 1681.21  5395.2 1687.75  5401.6 1689.03
  5406.3 1689.09  5471.6 1685.63  5475.8 1686.89  5484.3 1691.55  5488.6 1696.46
  5492.8 1699.78  5497.1 1701.97  5522.5 1706.67  5550.3 1709.32  5561.0 1710.77
#Mann=5,-1,0
  4463.9    0.07       0  5007.1    0.05       0  5011.2    0.07       0
  5406.3   0.063       0  5550.3   0.094       0
Bank Sta=5007.1,5011.2
Exp/Cntr=0.3,0.1

Type RM Length L Ch R = 1,18121,486,486,486
BEGIN DESCRIPTION:
Pass Creek 38.0
END DESCRIPTION:
XS GIS Cut Line= 3
      1932125.01     13884725.00      1932525.00     13884675.00
      1932925.00     13884375.00
#Sta/Elev= 30
  4592.6 1699.62  4644.7 1695.60  4665.9 1692.39  4693.1 1689.97  4720.3 1685.60
  4729.4 1683.15  4741.5 1680.90  4774.7 1677.14  4829.2 1673.65  4877.5 1671.88
  4962.2 1671.01  4980.3 1669.86  5011.2 1666.62  5011.4 1666.12  5015.0 1666.12
  5015.3 1666.62  5090.4 1671.08  5148.2 1672.73  5186.6 1671.66  5217.0 1671.85
  5257.9 1674.46  5272.5 1674.41  5297.0 1673.26  5362.5 1673.09  5404.1 1673.62
  5441.6 1676.30  5449.1 1678.60  5462.0 1683.82  5471.6 1687.42  5495.7 1688.04
#Mann=4,-1,0
  4592.6    0.07       0  5011.2    0.05       0  5015.3    0.07       0
  5462.0   0.035       0
Bank Sta=5011.2,5015.3
Exp/Cntr=0.3,0.1

Type RM Length L Ch R = 1,17635,429,429,429
BEGIN DESCRIPTION:
Pass Creek 37.0
END DESCRIPTION:
XS GIS Cut Line= 3
      1932225.00     13885375.00      1932625.00     13885125.00
      1933024.99     13884925.01
#Sta/Elev= 30
  4532.5 1700.44  4542.8 1698.85  4557.5 1697.93  4574.2 1695.35  4585.3 1692.68
  4624.2 1685.94  4642.4 1680.59  4651.2 1679.43  4675.7 1678.96  4680.8 1678.00
  4691.4 1674.10  4698.5 1672.92  4705.6 1672.40  4716.2 1673.00  4751.5 1669.73
  4822.3 1665.20  4942.9 1663.71  4979.4 1660.30  4979.7 1659.80  4983.6 1660.30
  5008.3 1662.71  5036.3 1664.14  5173.9 1664.94  5204.0 1664.64  5224.2 1663.48
  5308.0 1666.47  5354.6 1669.01  5401.7 1672.79  5432.1 1676.16  5451.4 1676.92
#Mann=6,-1,0
  4532.5    0.07       0  4574.2   0.035       0  4675.7    0.07       0
  4979.4    0.05       0  4983.6    0.07       0  5354.6     0.1       0
Bank Sta=4979.4,4983.6
Exp/Cntr=0.3,0.1

Type RM Length L Ch R = 1,17206,473,473,473
BEGIN DESCRIPTION:
Pass Creek 36.0
END DESCRIPTION:
XS GIS Cut Line= 3
      1932324.98     13885525.00      1932725.00     13885525.00
      1933124.98     13885375.01
#Sta/Elev= 30
  4595.8 1684.90  4606.6 1682.30  4624.6 1679.43  4639.6 1676.12  4669.6 1674.58
  4678.6 1670.77  4681.6 1670.33  4687.6 1670.79  4693.6 1669.94  4723.6 1667.51
  4774.6 1664.45  4822.6 1660.91  4843.6 1660.10  4894.6 1659.22  4936.6 1659.80
  4954.6 1659.02  4972.6 1659.02  4981.6 1658.42  5000.7 1656.00  5001.0 1655.50
  5005.0 1655.50  5005.3 1656.00  5047.9 1658.45  5105.6 1658.89  5185.7 1661.72
  5214.4 1662.16  5243.3 1663.48  5281.2 1664.35  5365.1 1669.03  5423.0 1673.48
#Mann=4,-1,0
  4595.8    0.07       0  5000.7    0.05       0  5005.3    0.07       0
  5281.2     0.1       0
Bank Sta=5000.7,5005.3
Exp/Cntr=0.3,0.1

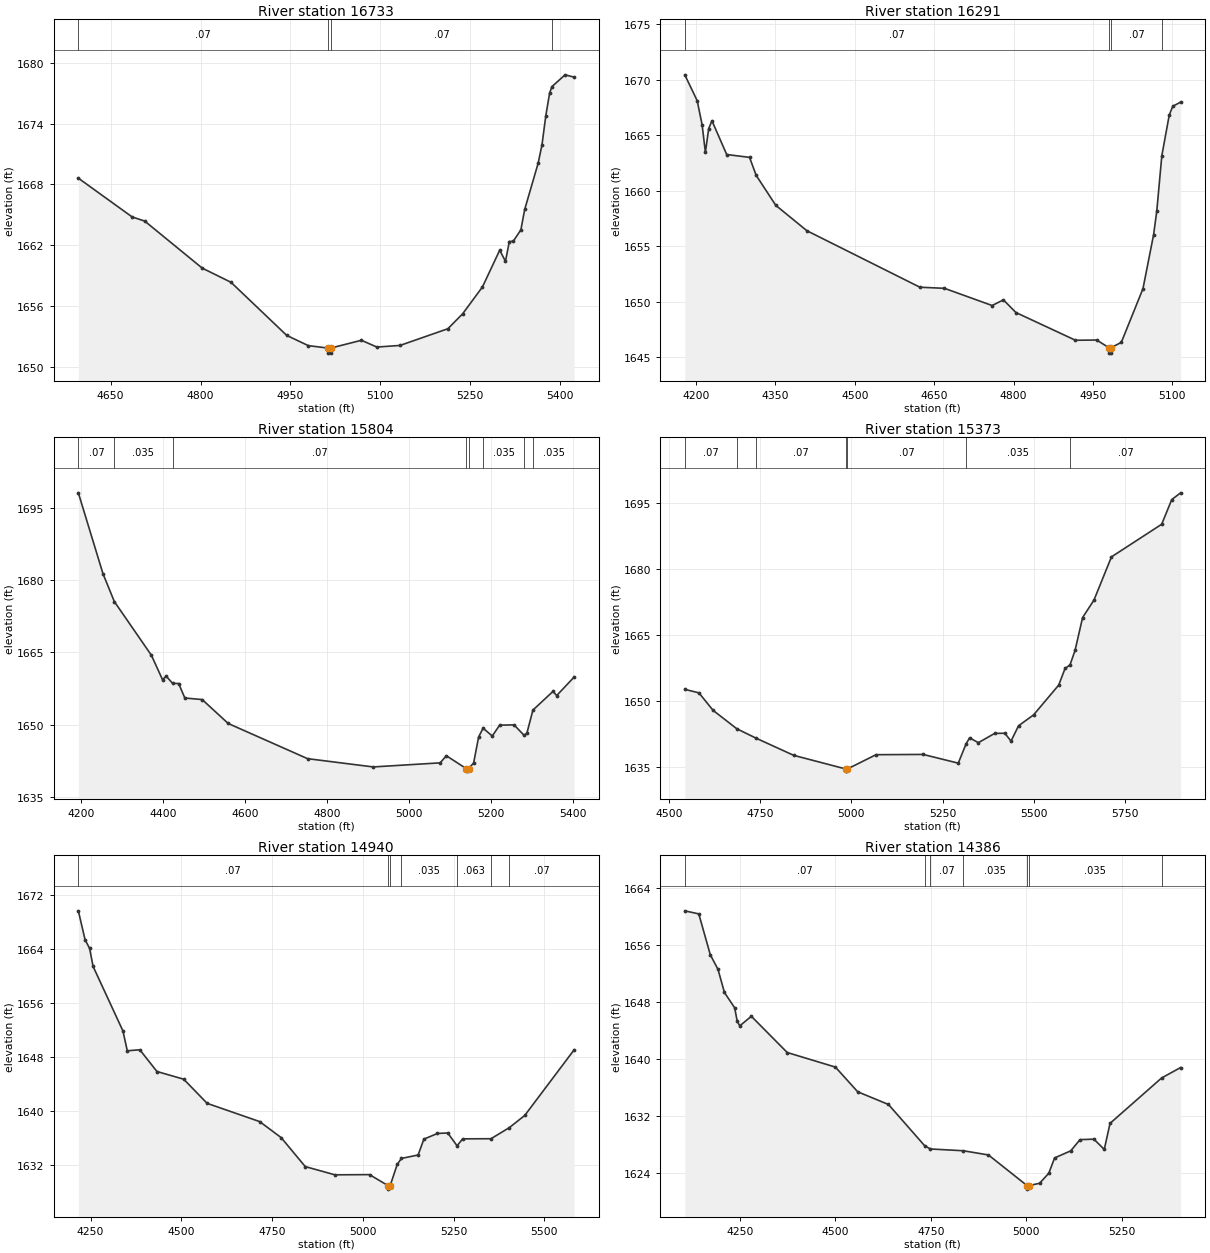
Type RM Length L Ch R = 1,16733,442,442,442
BEGIN DESCRIPTION:
Pass Creek 35.0
END DESCRIPTION:
XS GIS Cut Line= 3
      1932525.01     13885925.00      1932925.00     13885925.00
      1933325.01     13885775.00
#Sta/Elev= 30
  4596.1 1668.62  4685.8 1664.79  4706.8 1664.38  4802.8 1659.73  4850.8 1658.33
  4943.8 1653.08  4979.8 1652.07  5012.5 1651.83  5012.8 1651.33  5016.9 1651.33
  5017.2 1651.83  5068.4 1652.60  5094.1 1651.93  5132.8 1652.09  5212.6 1653.74
  5237.3 1655.22  5270.3 1657.87  5299.1 1661.50  5308.7 1660.40  5315.2 1662.36
  5321.6 1662.38  5334.4 1663.51  5340.8 1665.53  5363.2 1670.09  5369.6 1671.90
  5376.0 1674.79  5382.4 1677.04  5386.3 1677.67  5408.1 1678.83  5423.3 1678.60
#Mann=4,-1,0
  4596.1    0.07       0  5012.5    0.05       0  5017.2    0.07       0
  5386.3   0.063       0
Bank Sta=5012.5,5017.2
Exp/Cntr=0.3,0.1

Type RM Length L Ch R = 1,16291,487,487,487
BEGIN DESCRIPTION:
Pass Creek 34.0
END DESCRIPTION:
XS GIS Cut Line= 3
      1932475.00     13886375.00      1933275.00     13886175.00
      1933374.97     13886125.01
#Sta/Elev= 30
  4179.1 1670.44  4202.5 1668.11  4211.8 1665.94  4218.0 1663.45  4224.2 1665.59
  4230.4 1666.30  4258.2 1663.26  4301.4 1663.00  4313.9 1661.38  4350.9 1658.68
  4409.7 1656.39  4623.1 1651.30  4669.5 1651.20  4759.5 1649.65  4780.8 1650.16
  4804.4 1649.02  4916.9 1646.52  4957.0 1646.54  4979.7 1645.86  4980.1 1645.36
  4984.2 1645.36  4984.5 1645.86  5003.5 1646.33  5044.4 1651.17  5064.5 1656.04
  5070.5 1658.18  5080.0 1663.15  5094.0 1666.81  5100.7 1667.61  5115.5 1667.98
#Mann=4,-1,0
  4179.1    0.07       0  4979.7    0.05       0  4984.5    0.07       0
  5080.0   0.035       0
Bank Sta=4979.7,4984.5
Exp/Cntr=0.3,0.1

Type RM Length L Ch R = 1,15804,431,431,431
BEGIN DESCRIPTION:
Pass Creek 33.0
END DESCRIPTION:
XS GIS Cut Line= 3
      1932374.97     13886725.00      1933175.00     13886625.00
      1933575.03     13886575.00
#Sta/Elev= 30
  4193.4 1698.10  4253.6 1681.29  4281.2 1675.53  4371.6 1664.38  4398.8 1659.30
  4407.8 1660.04  4423.1 1658.56  4438.1 1658.50  4453.2 1655.50  4495.5 1655.18
  4559.0 1650.21  4752.5 1642.91  4912.7 1641.19  5076.0 1642.04  5091.1 1643.52
  5140.0 1640.82  5140.4 1640.32  5145.1 1640.82  5157.6 1642.01  5169.7 1647.38
  5180.6 1649.25  5203.0 1647.61  5221.1 1649.87  5256.3 1649.92  5280.9 1647.73
  5287.6 1648.23  5302.2 1652.99  5351.1 1656.87  5360.2 1656.01  5402.8 1659.86
#Mann=8,-1,0
  4193.4    0.07       0  4281.2   0.035       0  4423.1    0.07       0
  5140.0    0.05       0  5145.1    0.07       0  5180.6   0.035       0
  5280.9   0.063       0  5302.2   0.035       0
Bank Sta=5140,5145.1
Exp/Cntr=0.3,0.1

Type RM Length L Ch R = 1,15373,433,433,433
BEGIN DESCRIPTION:
Pass Creek 32.0
END DESCRIPTION:
XS GIS Cut Line= 4
      1932674.97     13886824.98      1932990.00     13887021.88
      1933178.93     13887016.54      1933874.97     13886625.02
#Sta/Elev= 30
  4543.5 1652.60  4582.2 1651.81  4621.1 1647.83  4686.2 1643.65  4738.9 1641.52
  4841.8 1637.63  4984.2 1634.54  4984.6 1634.04  4989.3 1634.54  5067.8 1637.77
  5196.7 1637.83  5293.1 1635.85  5314.3 1640.18  5324.1 1641.60  5348.2 1640.50
  5392.9 1642.60  5420.8 1642.64  5437.7 1640.85  5458.3 1644.33  5499.6 1646.81
  5568.5 1653.58  5585.8 1657.34  5599.4 1658.15  5613.2 1661.43  5633.9 1668.90
  5665.1 1672.87  5713.0 1682.67  5850.7 1690.08  5878.3 1695.68  5902.6 1697.21
#Mann=7,-1,0
  4543.5    0.07       0  4686.2   0.035       0  4738.9    0.07       0
  4984.2    0.05       0  4989.3    0.07       0  5314.3   0.035       0
  5599.4    0.07       0
Bank Sta=4984.2,4989.3
Exp/Cntr=0.3,0.1

Type RM Length L Ch R = 1,14940,554,554,554
BEGIN DESCRIPTION:
Pass Creek 31.0
END DESCRIPTION:
XS GIS Cut Line= 4
      1932525.02     13887175.01      1933218.00     13887391.56
      1933436.80     13887313.20      1933724.99     13887025.01
#Sta/Elev= 30
  4216.2 1669.71  4234.8 1665.42  4247.3 1664.14  4256.8 1661.48  4339.1 1651.91
  4351.1 1648.97  4385.6 1649.12  4432.8 1645.90  4506.5 1644.76  4571.1 1641.18
  4715.7 1638.48  4774.9 1636.11  4841.4 1631.81  4923.1 1630.59  5018.4 1630.62
  5070.1 1628.97  5070.4 1628.47  5075.2 1628.97  5094.9 1632.16  5106.5 1633.02
  5152.3 1633.53  5168.2 1635.88  5205.7 1636.72  5234.0 1636.79  5259.6 1634.89
  5275.0 1635.92  5353.1 1635.94  5403.5 1637.58  5446.1 1639.39  5582.2 1649.12
#Mann=7,-1,0
  4216.2    0.07       0  5070.1    0.05       0  5075.2    0.07       0
  5106.5   0.035       0  5259.6   0.063       0  5353.1   0.035       0
  5403.5    0.07       0
Bank Sta=5070.1,5075.2
Exp/Cntr=0.3,0.1

Type RM Length L Ch R = 1,14386,192,192,192
BEGIN DESCRIPTION:
Pass Creek 30.0
END DESCRIPTION:
XS GIS Cut Line= 3
      1932525.04     13887475.02      1933325.00     13887875.00
      1933725.00     13887825.00
#Sta/Elev= 30
  4106.5 1660.79  4143.1 1660.36  4173.3 1654.61  4193.4 1652.57  4210.2 1649.32
  4237.0 1647.17  4243.7 1645.27  4250.4 1644.63  4280.6 1645.98  4374.5 1640.89
  4500.7 1638.84  4559.0 1635.37  4639.5 1633.59  4734.4 1627.78  4749.4 1627.34
  4835.3 1627.09  4901.1 1626.50  5002.1 1622.20  5002.5 1621.70  5007.3 1622.20
  5034.9 1622.52  5059.1 1623.94  5074.2 1626.08  5116.5 1627.08  5140.7 1628.65
  5177.0 1628.72  5204.2 1627.28  5219.3 1630.94  5354.2 1637.31  5404.0 1638.78
#Mann=7,-1,0
  4106.5    0.07       0  4734.4   0.035       0  4749.4    0.07       0
  4835.3   0.035       0  5002.1   0.035       0  5007.3   0.035       0
  5354.2    0.07       0
Bank Sta=5002.1,5007.3
Exp/Cntr=0.3,0.1