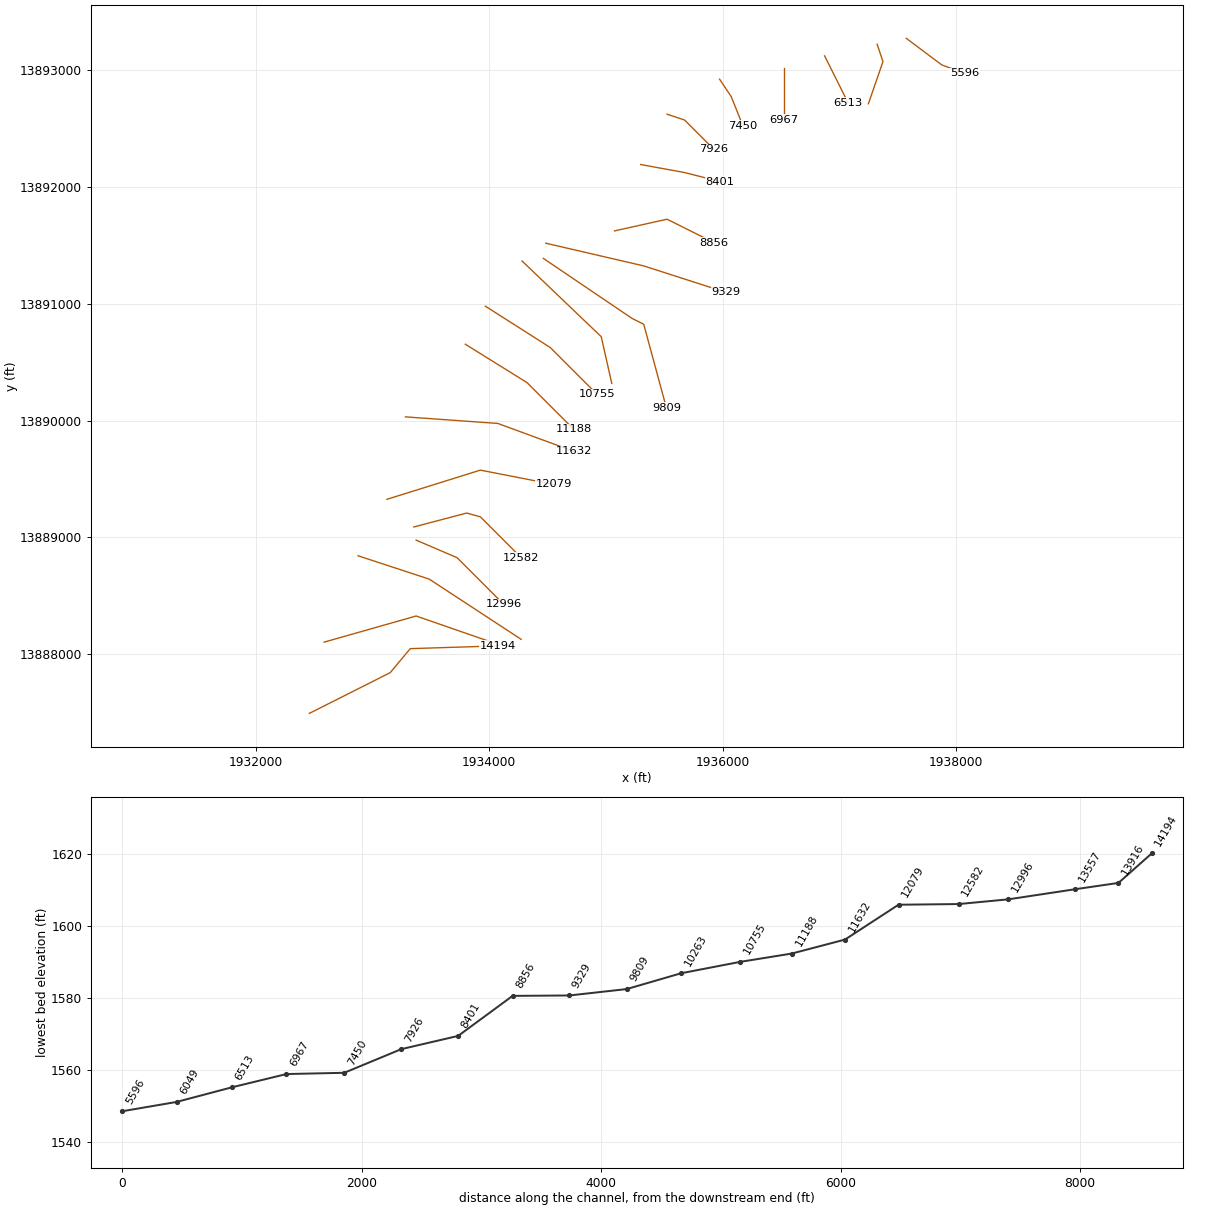
HEC-RAS study Pass Creek.prj: Pass Creek Base Level Engineering

--- Pass Creek.g01 (geometry) --- (continued)

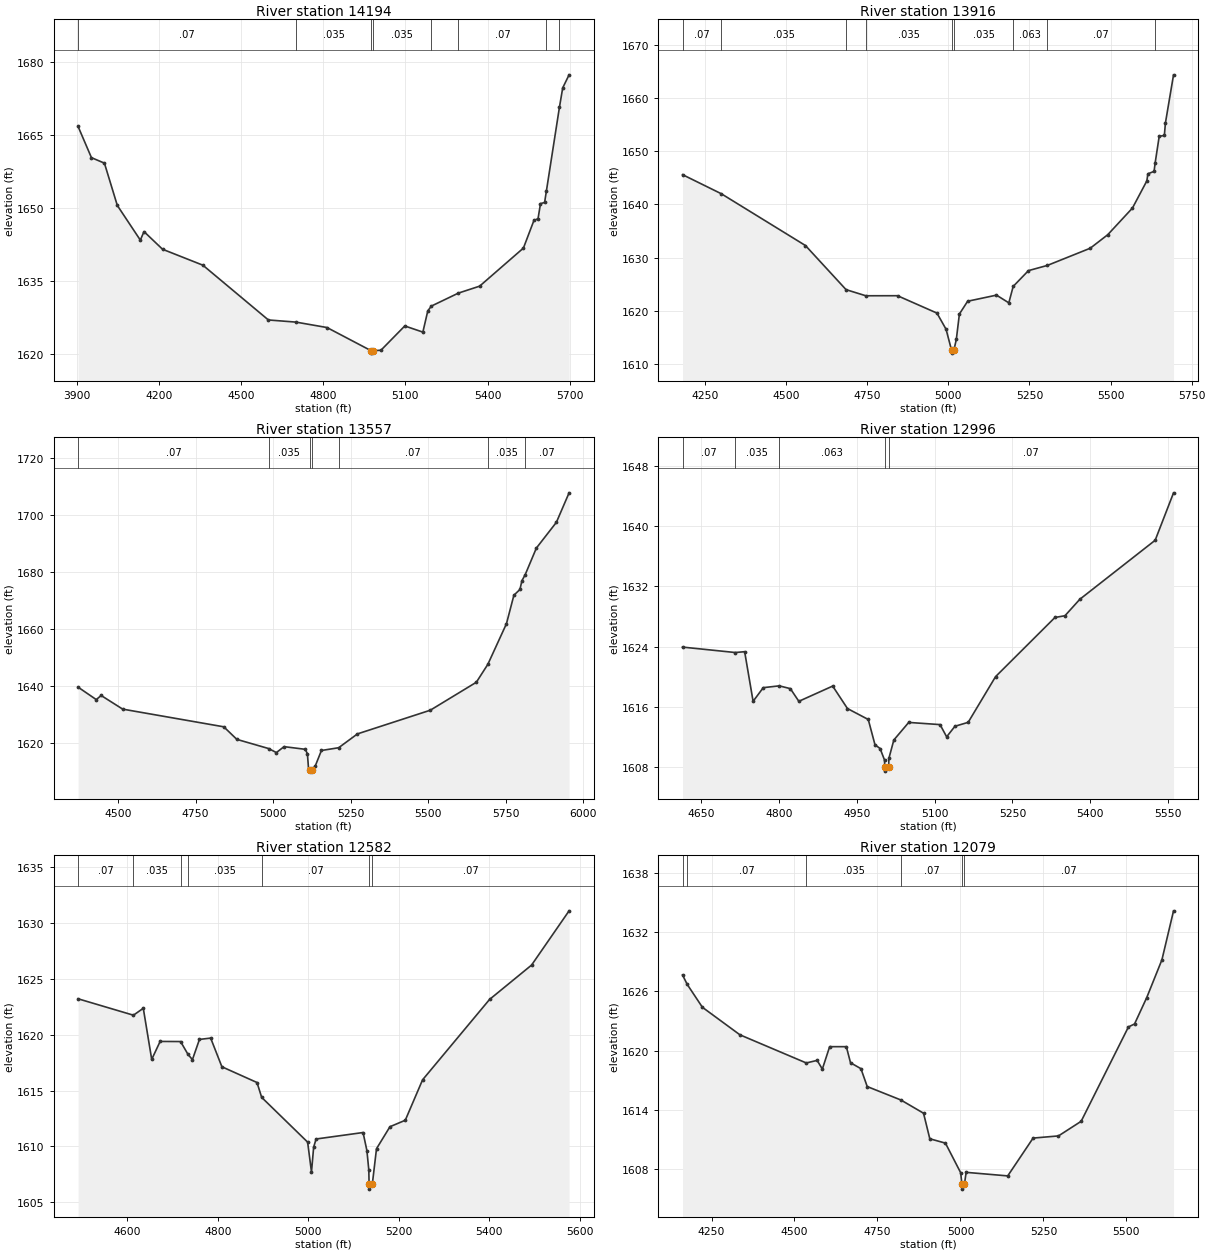
Type RM Length L Ch R = 1,14194,278,278,278
BEGIN DESCRIPTION:
Mapping XS 5269ea5a
END DESCRIPTION:
XS GIS Cut Line= 4
      1932459.96     13887490.64      1933152.64     13887839.59
      1933324.51     13888045.31      1934071.96     13888068.75
#Sta/Elev= 30
  3905.8 1666.71  3954.5 1660.32  4001.9 1659.19  4048.9 1650.52  4132.9 1643.41
  4146.3 1645.16  4213.9 1641.54  4361.1 1638.27  4600.1 1627.04  4700.7 1626.60
  4813.9 1625.49  4974.8 1620.74  4975.3 1620.24  4980.6 1620.74  5010.8 1620.83
  5097.8 1625.81  5163.8 1624.55  5181.8 1628.91  5195.0 1629.89  5293.5 1632.55
  5370.9 1633.97  5530.7 1641.78  5569.0 1647.44  5584.0 1647.80  5593.0 1650.89
  5608.0 1651.13  5614.5 1653.47  5662.1 1670.65  5674.1 1674.63  5697.3 1677.30
#Mann=8,-1,0
  3905.8    0.07       0  4700.7   0.035       0  4974.8   0.035       0
  4980.6   0.035       0  5195.0   0.063       0  5293.5    0.07       0
  5614.5   0.035       0  5662.1    0.07       0
Bank Sta=4974.8,4980.6
Exp/Cntr=0.3,0.1

Type RM Length L Ch R = 1,13916,359,359,359
BEGIN DESCRIPTION:
Pass Creek 29.0
END DESCRIPTION:
XS GIS Cut Line= 3
      1932586.26     13888101.02      1933375.00     13888325.00
      1934030.47     13888097.66
#Sta/Elev= 30
  4180.5 1645.61  4300.0 1642.02  4559.4 1632.28  4684.6 1623.98  4745.5 1622.83
  4843.2 1622.84  4964.8 1619.57  4992.9 1616.53  5010.0 1612.54  5010.5 1612.04
  5016.8 1612.54  5024.5 1614.61  5034.0 1619.40  5059.4 1621.80  5148.3 1622.95
  5186.4 1621.50  5199.8 1624.59  5246.9 1627.56  5305.3 1628.54  5437.3 1631.77
  5491.3 1634.31  5567.5 1639.33  5611.9 1644.44  5615.1 1645.77  5634.2 1646.23
  5637.3 1647.74  5650.0 1652.82  5665.9 1652.99  5669.1 1655.31  5694.2 1664.39
#Mann=9,-1,0
  4180.5    0.07       0  4300.0   0.035       0  4684.6    0.07       0
  4745.5   0.035       0  5010.0   0.035       0  5016.8   0.035       0
  5199.8   0.063       0  5305.3    0.07       0  5637.3   0.035       0
Bank Sta=5010,5016.8
Exp/Cntr=0.3,0.1

Type RM Length L Ch R = 1,13557,561,561,561
BEGIN DESCRIPTION:
Pass Creek 28.0
END DESCRIPTION:
XS GIS Cut Line= 3
      1932877.39     13888841.01      1933486.92     13888641.13
      1934274.98     13888125.01
#Sta/Elev= 30
  4371.1 1639.73  4429.7 1635.37  4445.5 1636.81  4514.9 1632.03  4841.0 1625.83
  4883.1 1621.43  4985.7 1618.21  5010.6 1616.80  5035.4 1618.88  5103.6 1617.95
  5110.7 1616.40  5114.3 1611.19  5117.9 1610.80  5118.4 1610.30  5125.1 1610.80
  5135.8 1612.05  5155.9 1617.53  5211.4 1618.50  5272.1 1623.35  5507.0 1631.65
  5655.5 1641.45  5692.7 1647.75  5752.7 1661.99  5776.6 1671.95  5796.1 1673.97
  5802.5 1677.04  5813.0 1679.14  5849.1 1688.48  5913.7 1697.51  5954.6 1707.84
#Mann=7,-1,0
  4371.1    0.07       0  4985.7   0.035       0  5117.9   0.035       0
  5125.1   0.035       0  5211.4    0.07       0  5692.7   0.035       0
  5813.0    0.07       0
Bank Sta=5117.9,5125.1
Exp/Cntr=0.3,0.1

Type RM Length L Ch R = 1,12996,414,414,414
BEGIN DESCRIPTION:
Pass Creek 27.0
END DESCRIPTION:
XS GIS Cut Line= 3
      1933375.00     13888975.00      1933725.00     13888825.00
      1934125.02     13888424.98
#Sta/Elev= 30
  4614.1 1623.93  4715.7 1623.21  4733.8 1623.32  4750.1 1616.74  4769.7 1618.55
  4800.5 1618.79  4821.9 1618.42  4838.3 1616.74  4903.5 1618.76  4932.0 1615.78
  4972.1 1614.33  4985.1 1610.97  4994.9 1610.48  5003.4 1608.96  5004.0 1607.98
  5004.5 1607.48  5011.3 1607.98  5011.9 1609.18  5021.4 1611.61  5050.1 1613.94
  5110.5 1613.65  5123.2 1612.03  5139.2 1613.43  5164.7 1613.95  5217.5 1620.01
  5332.0 1627.86  5351.3 1628.09  5379.9 1630.27  5525.2 1638.10  5560.6 1644.39
#Mann=5,-1,0
  4614.1    0.07       0  4715.7   0.035       0  4800.5   0.063       0
  5004.0    0.05       0  5011.3    0.07       0
Bank Sta=5004,5011.3
Exp/Cntr=0.3,0.1

Type RM Length L Ch R = 1,12582,503,503,503
BEGIN DESCRIPTION:
Pass Creek 26.0
END DESCRIPTION:
XS GIS Cut Line= 4
      1933354.71     13889087.77      1933808.28     13889207.40
      1933925.46     13889174.54      1934275.00     13888825.00
#Sta/Elev= 30
  4491.1 1623.22  4613.4 1621.75  4635.2 1622.37  4653.8 1617.79  4672.4 1619.40
  4717.6 1619.39  4734.0 1618.24  4743.8 1617.77  4759.3 1619.58  4784.1 1619.70
  4808.9 1617.13  4886.5 1615.72  4896.8 1614.39  4998.4 1610.38  5006.9 1607.70
  5011.7 1609.93  5017.1 1610.66  5120.9 1611.24  5129.4 1609.62  5133.6 1607.88
  5134.2 1606.67  5134.7 1606.17  5141.5 1606.67  5150.6 1609.79  5180.3 1611.76
  5214.2 1612.34  5252.4 1615.96  5400.4 1623.16  5493.3 1626.24  5576.2 1631.10
#Mann=7,-1,0
  4491.1    0.07       0  4613.4   0.035       0  4717.6   0.063       0
  4734.0   0.035       0  4896.8    0.07       0  5134.2    0.05       0
  5141.5    0.07       0
Bank Sta=5134.2,5141.5
Exp/Cntr=0.3,0.1

Type RM Length L Ch R = 1,12079,447,447,447
BEGIN DESCRIPTION:
Pass Creek 25.0
END DESCRIPTION:
XS GIS Cut Line= 3
      1933124.97     13889324.99      1933925.00     13889575.00
      1934554.40     13889452.48
#Sta/Elev= 30
  4162.7 1627.67  4176.9 1626.71  4222.5 1624.40  4335.6 1621.61  4535.5 1618.76
  4568.2 1619.02  4583.9 1618.14  4605.9 1620.41  4656.2 1620.41  4668.8 1618.78
  4700.2 1618.18  4719.1 1616.37  4820.5 1615.01  4888.8 1613.67  4907.7 1611.08
  4954.8 1610.64  5000.6 1607.65  5004.5 1606.48  5005.0 1605.98  5012.0 1606.48
  5017.2 1607.68  5142.5 1607.32  5218.9 1611.15  5295.4 1611.37  5363.7 1612.85
  5506.2 1622.41  5524.6 1622.71  5561.3 1625.38  5607.1 1629.21  5642.1 1634.17
#Mann=6,-1,0
  4162.7   0.035       0  4176.9    0.07       0  4535.5   0.035       0
  4820.5    0.07       0  5004.5    0.05       0  5012.0    0.07       0
Bank Sta=5004.5,5012
Exp/Cntr=0.3,0.1

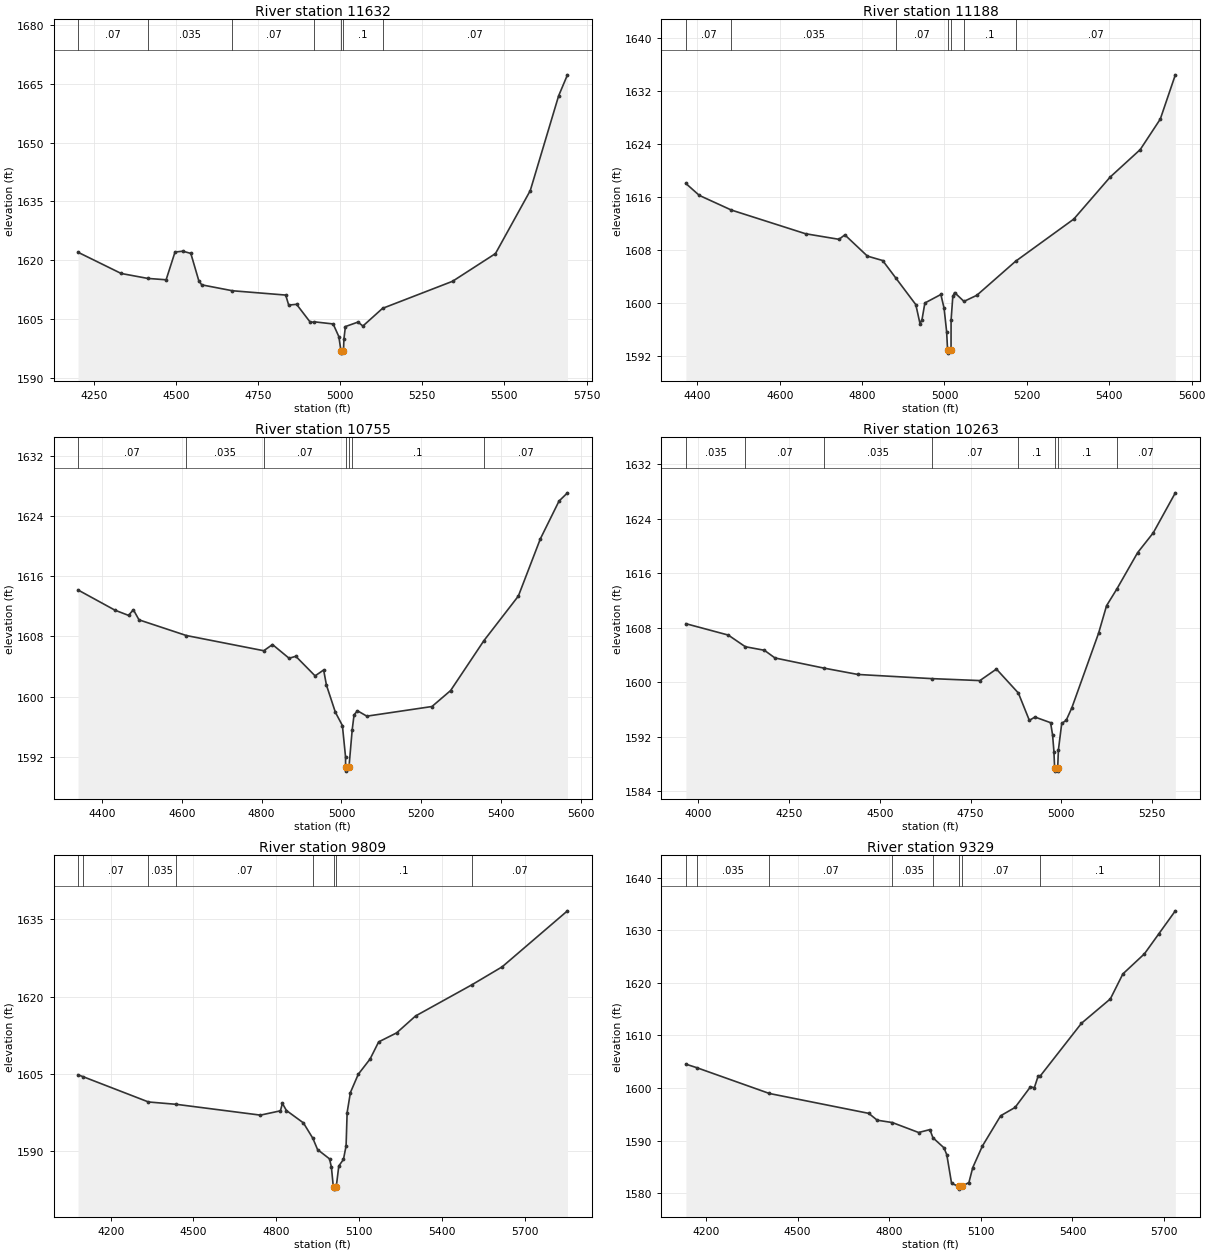
Type RM Length L Ch R = 1,11632,444,444,444
BEGIN DESCRIPTION:
Pass Creek 24.0
END DESCRIPTION:
XS GIS Cut Line= 3
      1933283.61     13890031.43      1934075.00     13889975.00
      1934728.33     13889735.06
#Sta/Elev= 30
  4202.4 1622.03  4333.7 1616.62  4414.4 1615.36  4470.5 1615.01  4497.6 1622.09
  4521.6 1622.30  4545.7 1621.73  4569.8 1614.81  4578.8 1613.72  4672.4 1612.21
  4834.4 1611.11  4843.5 1608.56  4867.5 1608.75  4909.6 1604.13  4922.0 1604.28
  4978.8 1603.74  4996.1 1600.52  5002.7 1596.80  5003.2 1596.30  5010.2 1596.80
  5011.5 1599.85  5016.1 1603.08  5054.4 1604.22  5069.3 1603.21  5129.1 1607.72
  5342.0 1614.62  5472.7 1621.69  5578.6 1637.76  5664.9 1661.93  5691.8 1667.29
#Mann=7,-1,0
  4202.4    0.07       0  4414.4   0.035       0  4672.4    0.07       0
  4922.0     0.1       0  5002.7    0.05       0  5010.2     0.1       0
  5129.1    0.07       0
Bank Sta=5002.7,5010.2
Exp/Cntr=0.3,0.1

Type RM Length L Ch R = 1,11188,433,433,433
BEGIN DESCRIPTION:
Pass Creek 23.0
END DESCRIPTION:
XS GIS Cut Line= 3
      1933796.34     13890653.71      1934325.00     13890325.00
      1934725.00     13889925.00
#Sta/Elev= 30
  4372.2 1618.00  4404.8 1616.20  4482.7 1613.99  4662.7 1610.42  4743.9 1609.58
  4758.1 1610.25  4812.8 1607.05  4849.9 1606.38  4881.9 1603.74  4930.4 1599.73
  4940.6 1596.85  4945.3 1597.44  4952.4 1599.98  4991.2 1601.26  4999.0 1599.19
  5005.2 1595.66  5007.5 1592.92  5008.0 1592.42  5015.9 1592.92  5016.0 1597.37
  5020.2 1600.97  5024.5 1601.55  5047.3 1600.22  5078.5 1601.14  5172.4 1606.26
  5313.9 1612.63  5402.1 1618.96  5475.2 1623.11  5523.9 1627.71  5560.4 1634.38
#Mann=7,-1,0
  4372.2    0.07       0  4482.7   0.035       0  4881.9    0.07       0
  5007.5    0.05       0  5015.9    0.07       0  5047.3     0.1       0
  5172.4    0.07       0
Bank Sta=5007.5,5015.9
Exp/Cntr=0.3,0.1

Type RM Length L Ch R = 1,10755,492,492,492
BEGIN DESCRIPTION:
Pass Creek 22.0
END DESCRIPTION:
XS GIS Cut Line= 3
      1933968.14     13890979.61      1934525.00     13890625.00
      1934925.02     13890224.98
#Sta/Elev= 30
  4340.1 1614.16  4432.5 1611.48  4466.7 1610.78  4478.7 1611.54  4492.9 1610.19
  4611.3 1608.11  4805.3 1606.09  4827.2 1606.91  4868.8 1605.09  4885.6 1605.35
  4933.9 1602.75  4955.3 1603.53  4962.4 1601.51  4984.7 1597.92  5002.3 1596.15
  5010.2 1591.97  5010.3 1590.60  5010.8 1590.10  5018.7 1590.60  5026.9 1595.62
  5031.5 1597.57  5039.9 1598.12  5063.5 1597.40  5226.6 1598.68  5273.3 1600.80
  5356.6 1607.42  5443.0 1613.35  5498.1 1620.95  5544.8 1625.96  5566.0 1627.06
#Mann=7,-1,0
  4340.1    0.07       0  4611.3   0.035       0  4805.3    0.07       0
  5010.3    0.05       0  5018.7    0.07       0  5026.9     0.1       0
  5356.6    0.07       0
Bank Sta=5010.3,5018.7
Exp/Cntr=0.3,0.1

Type RM Length L Ch R = 1,10263,454,454,454
BEGIN DESCRIPTION:
Pass Creek 21.0
END DESCRIPTION:
XS GIS Cut Line= 3
      1934282.64     13891366.89      1934960.86     13890718.33
      1935051.21     13890318.31
#Sta/Elev= 30
  3965.5 1608.58  4082.3 1606.91  4129.3 1605.20  4181.7 1604.68  4211.0 1603.55
  4345.0 1602.07  4439.3 1601.13  4642.6 1600.52  4775.5 1600.23  4821.1 1601.92
  4881.6 1598.40  4911.8 1594.39  4927.2 1594.88  4970.3 1594.05  4975.8 1592.26
  4979.5 1589.82  4981.4 1587.44  4981.9 1586.94  4989.4 1586.94  4989.9 1587.44
  4991.8 1590.03  5001.0 1593.94  5013.3 1594.40  5028.7 1596.21  5102.5 1607.18
  5124.5 1611.22  5152.7 1613.66  5210.2 1619.02  5253.2 1621.92  5314.0 1627.79
#Mann=8,-1,0
  3965.5   0.035       0  4129.3    0.07       0  4345.0   0.035       0
  4642.6    0.07       0  4881.6     0.1       0  4981.4    0.05       0
  4989.9     0.1       0  5152.7    0.07       0
Bank Sta=4981.4,4989.9
Exp/Cntr=0.3,0.1

Type RM Length L Ch R = 1,9809,480,480,480
BEGIN DESCRIPTION:
Pass Creek 20.0
END DESCRIPTION:
XS GIS Cut Line= 4
      1934464.53     13891389.48      1935225.00     13890875.00
      1935325.00     13890825.00      1935519.69     13890107.30
#Sta/Elev= 30
  4081.8 1604.78  4099.0 1604.44  4337.1 1599.50  4438.1 1599.04  4742.8 1596.94
  4815.3 1597.78  4822.4 1599.24  4837.0 1597.84  4898.6 1595.43  4932.9 1592.42
  4949.9 1590.24  4993.1 1588.44  5000.0 1586.83  5006.7 1583.12  5009.2 1583.05
  5009.7 1582.55  5017.7 1583.05  5026.8 1587.05  5043.6 1588.32  5053.2 1590.95
  5057.0 1597.44  5068.9 1601.34  5097.3 1604.88  5140.2 1607.86  5171.2 1611.18
  5236.5 1612.94  5304.9 1616.22  5508.5 1622.27  5618.8 1625.78  5855.4 1636.67
#Mann=8,-1,0
  4081.8   0.035       0  4099.0    0.07       0  4337.1   0.035       0
  4438.1    0.07       0  4932.9     0.1       0  5009.2    0.05       0
  5017.7     0.1       0  5508.5    0.07       0
Bank Sta=5009.2,5017.7
Exp/Cntr=0.3,0.1

Type RM Length L Ch R = 1,9329,473,473,473
BEGIN DESCRIPTION:
Pass Creek 19.0
END DESCRIPTION:
XS GIS Cut Line= 3
      1934485.58     13891519.60      1935325.00     13891325.00
      1936030.61     13891098.02
#Sta/Elev= 30
  4134.0 1604.54  4169.1 1603.88  4407.5 1598.96  4732.9 1595.18  4760.6 1593.88
  4810.3 1593.43  4896.2 1591.54  4933.1 1592.09  4943.1 1590.54  4979.3 1588.62
  4988.5 1587.30  5004.1 1581.88  5027.6 1581.27  5028.1 1580.77  5037.0 1581.27
  5060.9 1582.03  5073.5 1584.87  5105.0 1588.96  5164.8 1594.72  5212.1 1596.31
  5262.5 1600.23  5275.1 1600.05  5287.8 1602.30  5295.2 1602.34  5429.6 1612.32
  5524.1 1616.95  5565.1 1621.70  5635.8 1625.53  5682.2 1629.28  5736.9 1633.70
#Mann=9,-1,0
  4134.0    0.07       0  4169.1   0.035       0  4407.5    0.07       0
  4810.3   0.035       0  4943.1    0.07       0  5027.6    0.05       0
  5037.0    0.07       0  5295.2     0.1       0  5682.2    0.07       0
Bank Sta=5027.6,5037
Exp/Cntr=0.3,0.1

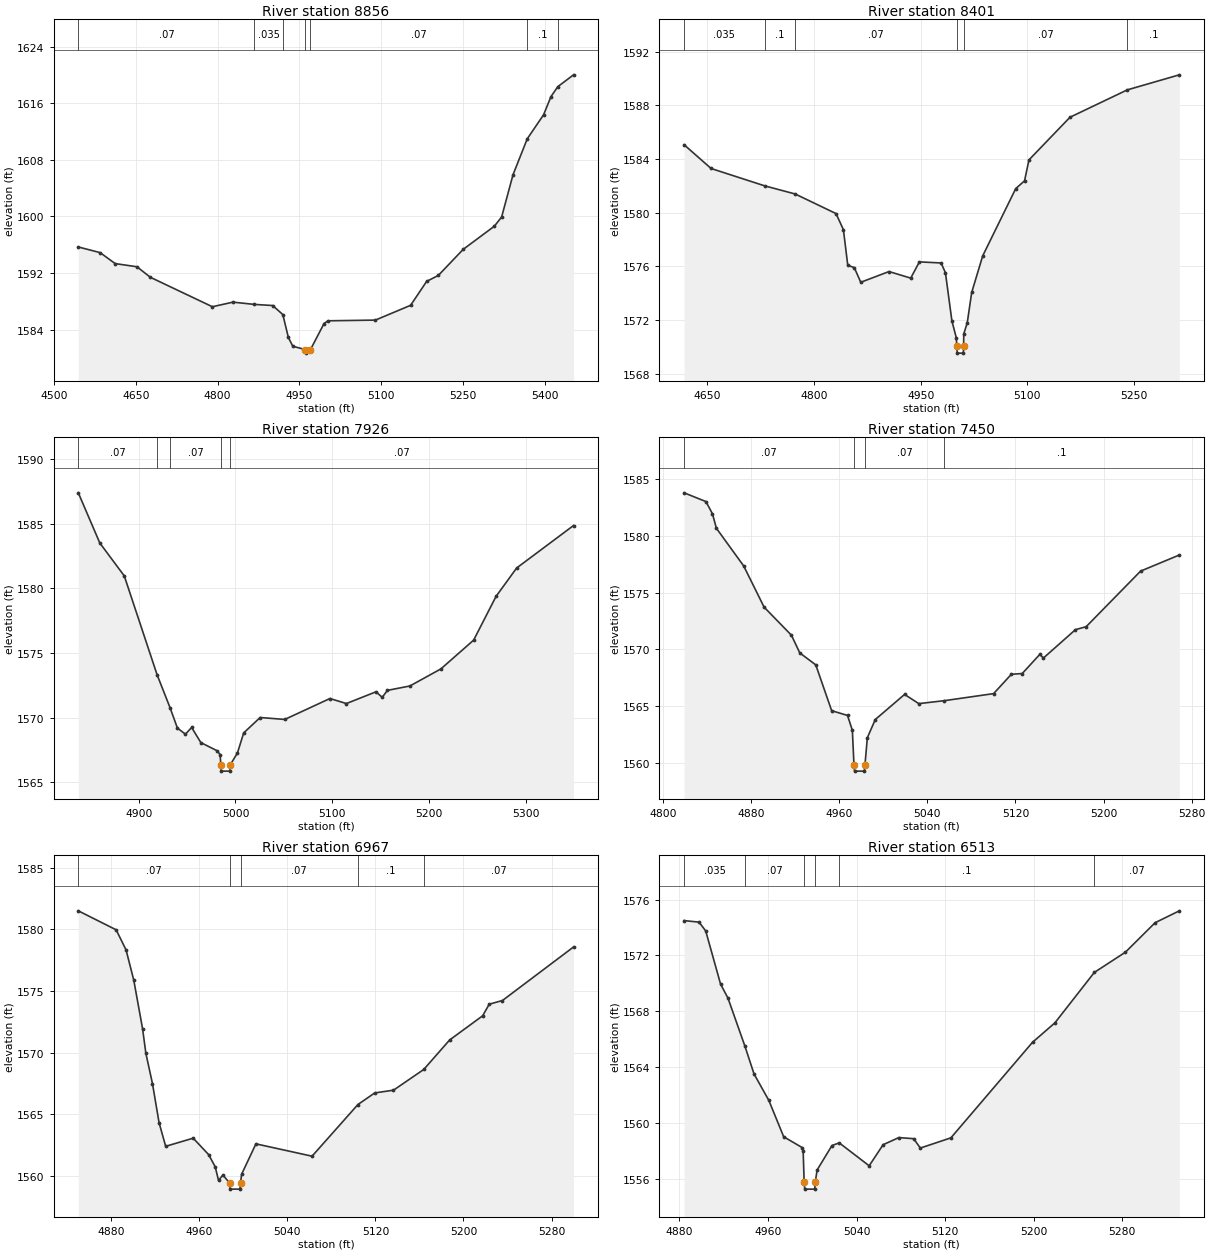
Type RM Length L Ch R = 1,8856,455,455,455
BEGIN DESCRIPTION:
Pass Creek 18.0
END DESCRIPTION:
XS GIS Cut Line= 3
      1935075.03     13891625.01      1935525.00     13891725.00
      1935925.04     13891524.98
#Sta/Elev= 30
  4544.5 1595.67  4584.5 1594.87  4612.1 1593.32  4652.1 1592.87  4676.7 1591.38
  4790.4 1587.22  4828.2 1587.87  4867.3 1587.55  4901.0 1587.39  4919.6 1586.11
  4929.7 1582.88  4937.9 1581.63  4960.8 1581.16  4961.3 1580.66  4970.3 1581.16
  4995.1 1584.84  5002.4 1585.23  5089.3 1585.33  5153.9 1587.42  5183.3 1590.80
  5204.8 1591.65  5250.3 1595.33  5307.4 1598.60  5320.8 1599.90  5341.7 1605.88
  5367.8 1610.96  5397.9 1614.38  5411.3 1616.93  5423.9 1618.34  5452.7 1620.01
#Mann=7,-1,0
  4544.5    0.07       0  4867.3   0.035       0  4919.6    0.07       0
  4960.8    0.05       0  4970.3    0.07       0  5367.8     0.1       0
  5423.9    0.07       0
Bank Sta=4960.8,4970.3
Exp/Cntr=0.3,0.1

Type RM Length L Ch R = 1,8401,475,475,475
BEGIN DESCRIPTION:
Pass Creek 17.0
END DESCRIPTION:
XS GIS Cut Line= 3
      1935298.73     13892193.61      1935675.00     13892125.00
      1935978.99     13892047.83
#Sta/Elev= 30
  4617.5 1585.07  4655.4 1583.30  4730.5 1582.01  4773.6 1581.40  4831.0 1579.94
  4841.4 1578.74  4847.5 1576.09  4856.7 1575.91  4865.8 1574.82  4905.5 1575.62
  4936.0 1575.13  4948.2 1576.34  4978.7 1576.26  4984.8 1575.53  4993.9 1571.94
  5000.0 1570.70  5000.9 1570.04  5001.4 1569.54  5009.9 1569.54  5010.4 1570.04
  5010.5 1570.96  5015.5 1571.81  5021.7 1574.06  5037.2 1576.79  5083.6 1581.80
  5096.0 1582.38  5102.2 1583.94  5159.9 1587.12  5240.5 1589.16  5313.6 1590.28
#Mann=6,-1,0
  4617.5   0.035       0  4730.5     0.1       0  4773.6    0.07       0
  5000.9    0.05       0  5010.4    0.07       0  5240.5     0.1       0
Bank Sta=5000.9,5010.4
Exp/Cntr=0.3,0.1

Type RM Length L Ch R = 1,7926,476,476,476
BEGIN DESCRIPTION:
Pass Creek 16.0
END DESCRIPTION:
XS GIS Cut Line= 3
      1935524.98     13892625.01      1935675.00     13892575.00
      1935925.01     13892324.99
#Sta/Elev= 30
  4837.6 1587.40  4859.8 1583.52  4885.1 1580.97  4919.0 1573.32  4932.4 1570.77
  4940.0 1569.19  4948.3 1568.72  4954.7 1569.24  4964.2 1568.07  4981.2 1567.43
  4984.1 1567.14  4984.9 1566.36  4985.4 1565.86  4994.2 1565.86  4994.7 1566.36
  5002.0 1567.26  5008.5 1568.82  5025.5 1570.01  5050.9 1569.86  5097.6 1571.48
  5114.6 1571.09  5145.2 1572.00  5151.6 1571.57  5157.0 1572.11  5180.2 1572.45
  5212.2 1573.77  5246.1 1576.00  5269.2 1579.38  5290.5 1581.58  5349.3 1584.87
#Mann=5,-1,0
  4837.6    0.07       0  4919.0     0.1       0  4932.4    0.07       0
  4984.9    0.05       0  4994.7    0.07       0
Bank Sta=4984.9,4994.7
Exp/Cntr=0.3,0.1

Type RM Length L Ch R = 1,7450,483,483,483
BEGIN DESCRIPTION:
Pass Creek 15.0
END DESCRIPTION:
XS GIS Cut Line= 3
      1935975.00     13892924.99      1936075.00     13892775.00
      1936174.99     13892525.03
#Sta/Elev= 30
  4819.3 1583.78  4839.1 1583.01  4845.0 1581.94  4848.6 1580.66  4873.4 1577.34
  4891.9 1573.72  4916.7 1571.25  4924.3 1569.69  4938.8 1568.64  4953.2 1564.61
  4967.6 1564.19  4972.0 1562.88  4973.5 1559.79  4974.0 1559.29  4982.9 1559.29
  4983.4 1559.79  4985.6 1562.23  4992.8 1563.83  5019.4 1566.04  5032.3 1565.23
  5055.5 1565.49  5100.2 1566.11  5116.3 1567.81  5126.2 1567.88  5142.2 1569.57
  5145.4 1569.24  5174.5 1571.74  5184.2 1572.00  5233.6 1576.89  5268.8 1578.31
#Mann=4,-1,0
  4819.3    0.07       0  4973.5    0.05       0  4983.4    0.07       0
  5055.5     0.1       0
Bank Sta=4973.5,4983.4
Exp/Cntr=0.3,0.1

Type RM Length L Ch R = 1,6967,454,454,454
BEGIN DESCRIPTION:
Pass Creek 14.0
END DESCRIPTION:
XS GIS Cut Line= 3
      1936525.00     13893025.03      1936525.00     13892875.00
      1936525.00     13892575.03
#Sta/Elev= 30
  4850.0 1581.50  4884.4 1579.96  4893.4 1578.33  4900.4 1575.88  4908.4 1571.94
  4911.4 1569.95  4917.4 1567.49  4923.4 1564.32  4929.4 1562.41  4954.4 1563.07
  4968.4 1561.74  4974.4 1560.75  4977.4 1559.65  4981.4 1560.08  4987.5 1559.44
  4988.0 1558.94  4996.9 1558.94  4997.4 1559.44  4998.4 1560.15  5011.4 1562.61
  5062.4 1561.61  5104.1 1565.80  5119.4 1566.74  5136.4 1566.96  5163.9 1568.64
  5187.4 1571.03  5217.4 1572.99  5223.4 1573.93  5235.4 1574.23  5300.0 1578.57
#Mann=5,-1,0
  4850.0    0.07       0  4987.5    0.05       0  4997.4    0.07       0
  5104.1     0.1       0  5163.9    0.07       0
Bank Sta=4987.5,4997.4
Exp/Cntr=0.3,0.1

Type RM Length L Ch R = 1,6513,464,464,464
BEGIN DESCRIPTION:
Pass Creek 13.0
END DESCRIPTION:
XS GIS Cut Line= 3
      1936874.99     13893125.03      1936925.00     13893025.00
      1937074.98     13892725.04
#Sta/Elev= 30
  4884.3 1574.49  4897.8 1574.38  4903.8 1573.75  4917.2 1569.95  4923.9 1568.94
  4939.3 1565.48  4947.4 1563.52  4960.8 1561.62  4974.2 1559.02  4991.0 1558.24
  4991.8 1557.98  4992.7 1555.77  4993.2 1555.27  5002.2 1555.27  5002.7 1555.77
  5004.4 1556.64  5017.8 1558.39  5024.4 1558.58  5051.4 1556.94  5064.0 1558.45
  5078.2 1558.96  5091.6 1558.88  5097.6 1558.21  5125.2 1558.94  5198.9 1565.78
  5219.1 1567.17  5254.7 1570.78  5282.8 1572.23  5309.6 1574.34  5331.5 1575.19
#Mann=6,-1,0
  4884.3   0.035       0  4939.3    0.07       0  4992.7    0.05       0
  5002.7    0.07       0  5024.4     0.1       0  5254.7    0.07       0
Bank Sta=4992.7,5002.7
Exp/Cntr=0.3,0.1

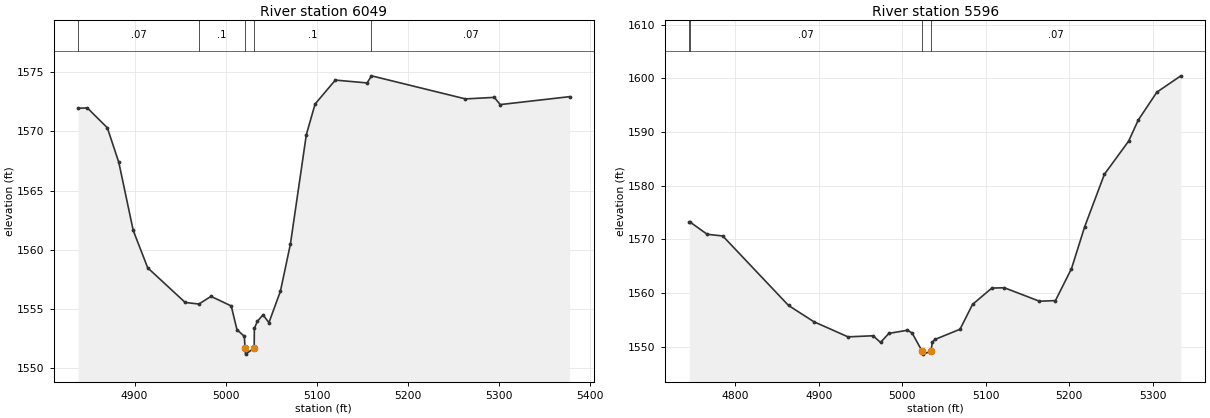
Type RM Length L Ch R = 1,6049,453,453,453
BEGIN DESCRIPTION:
Pass Creek 12.0
END DESCRIPTION:
XS GIS Cut Line= 3
      1937324.99     13893225.03      1937375.00     13893075.00
      1937250.07     13892714.59
#Sta/Elev= 30
  4838.0 1571.96  4848.1 1571.99  4870.1 1570.31  4882.7 1567.38  4898.5 1561.64
  4914.4 1558.48  4955.5 1555.56  4970.6 1555.42  4983.9 1556.07  5006.1 1555.26
  5012.4 1553.26  5020.5 1552.69  5021.3 1551.69  5021.8 1551.19  5031.3 1551.69
  5031.5 1553.36  5034.7 1553.95  5041.0 1554.51  5047.5 1553.85  5060.1 1556.50
  5071.1 1560.49  5088.6 1569.74  5098.2 1572.32  5120.4 1574.34  5155.3 1574.10
  5160.1 1574.70  5263.3 1572.75  5295.0 1572.88  5301.4 1572.27  5377.6 1572.94
#Mann=5,-1,0
  4838.0    0.07       0  4970.6     0.1       0  5021.3    0.05       0
  5031.3     0.1       0  5160.1    0.07       0
Bank Sta=5021.3,5031.3
Exp/Cntr=0.3,0.1

Type RM Length L Ch R = 1,5596,471,471,471
BEGIN DESCRIPTION:
Pass Creek 11.0
END DESCRIPTION:
XS GIS Cut Line= 4
      1937575.04     13893274.97      1937775.00     13893125.00
      1937879.51     13893047.01      1938075.01     13892975.00
#Sta/Elev= 30
  4745.1 1573.25  4745.7 1573.25  4766.4 1570.95  4785.1 1570.63  4863.9 1557.68
  4894.1 1554.66  4935.1 1551.83  4965.1 1552.03  4974.1 1550.79  4984.1 1552.48
  5006.3 1553.06  5011.8 1552.57  5024.1 1549.11  5024.6 1548.61  5034.3 1549.11
  5036.3 1550.87  5039.2 1551.34  5069.3 1553.25  5084.3 1557.88  5107.4 1560.92
  5122.4 1560.98  5164.4 1558.47  5183.6 1558.59  5202.8 1564.54  5218.7 1572.39
  5242.2 1582.12  5271.3 1588.32  5282.7 1592.21  5305.1 1597.44  5333.8 1600.48
#Mann=4,-1,0
  4745.1   0.035       0  4745.7    0.07       0  5024.1    0.05       0
  5034.3    0.07       0
Bank Sta=5024.1,5034.3
Exp/Cntr=0.3,0.1