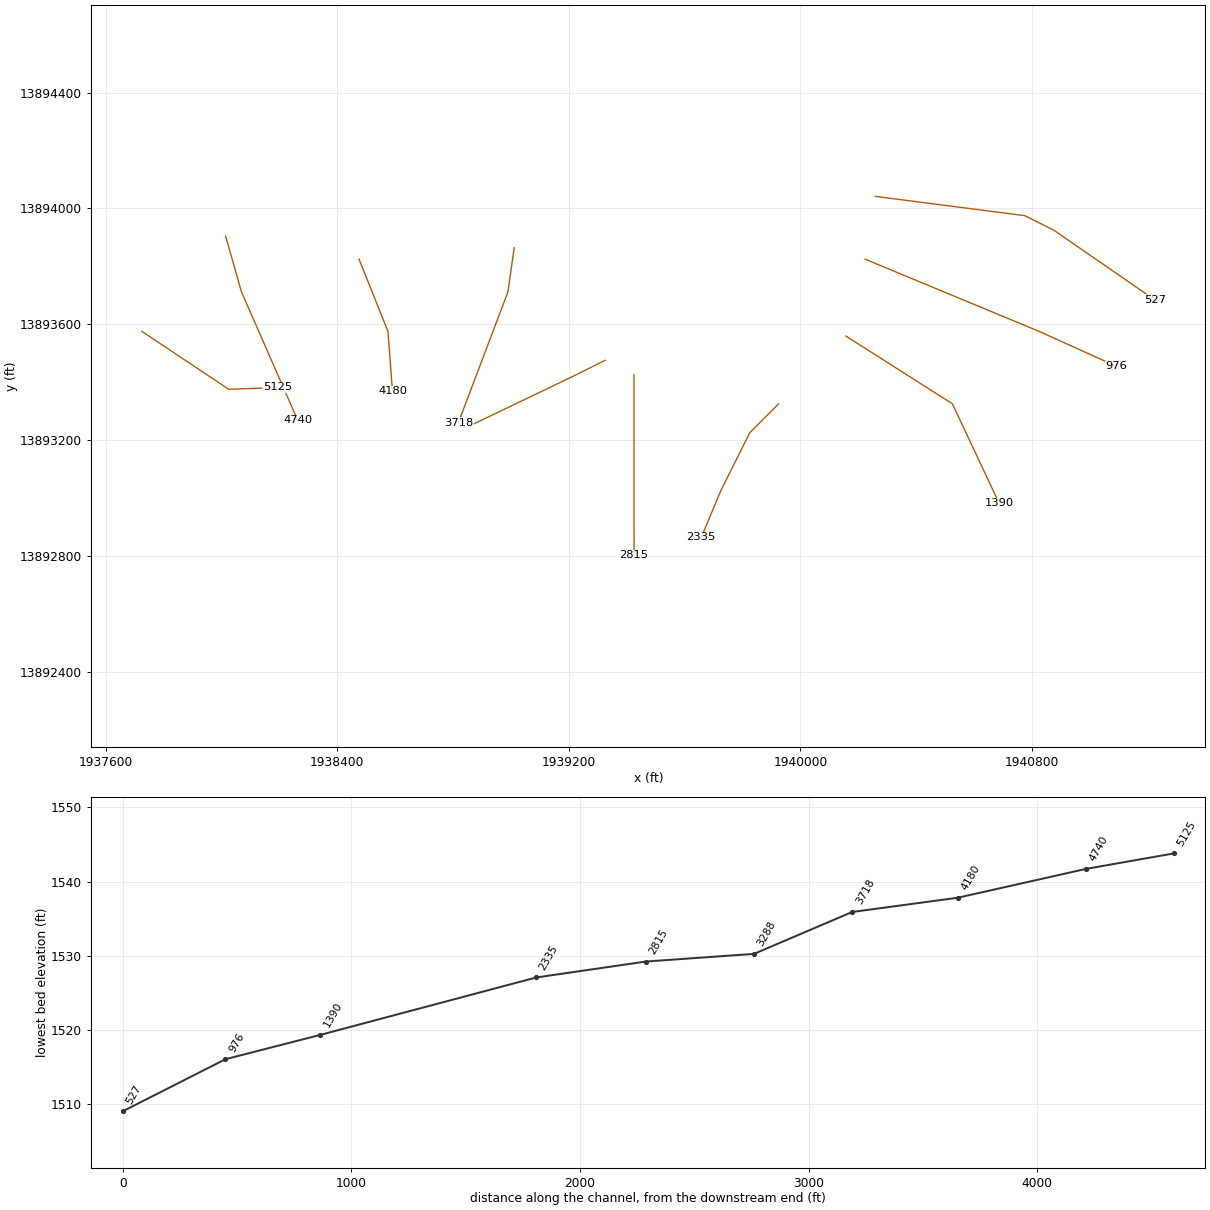
HEC-RAS study Pass Creek.prj: Pass Creek Base Level Engineering

--- Pass Creek.g01 (geometry) --- (continued)

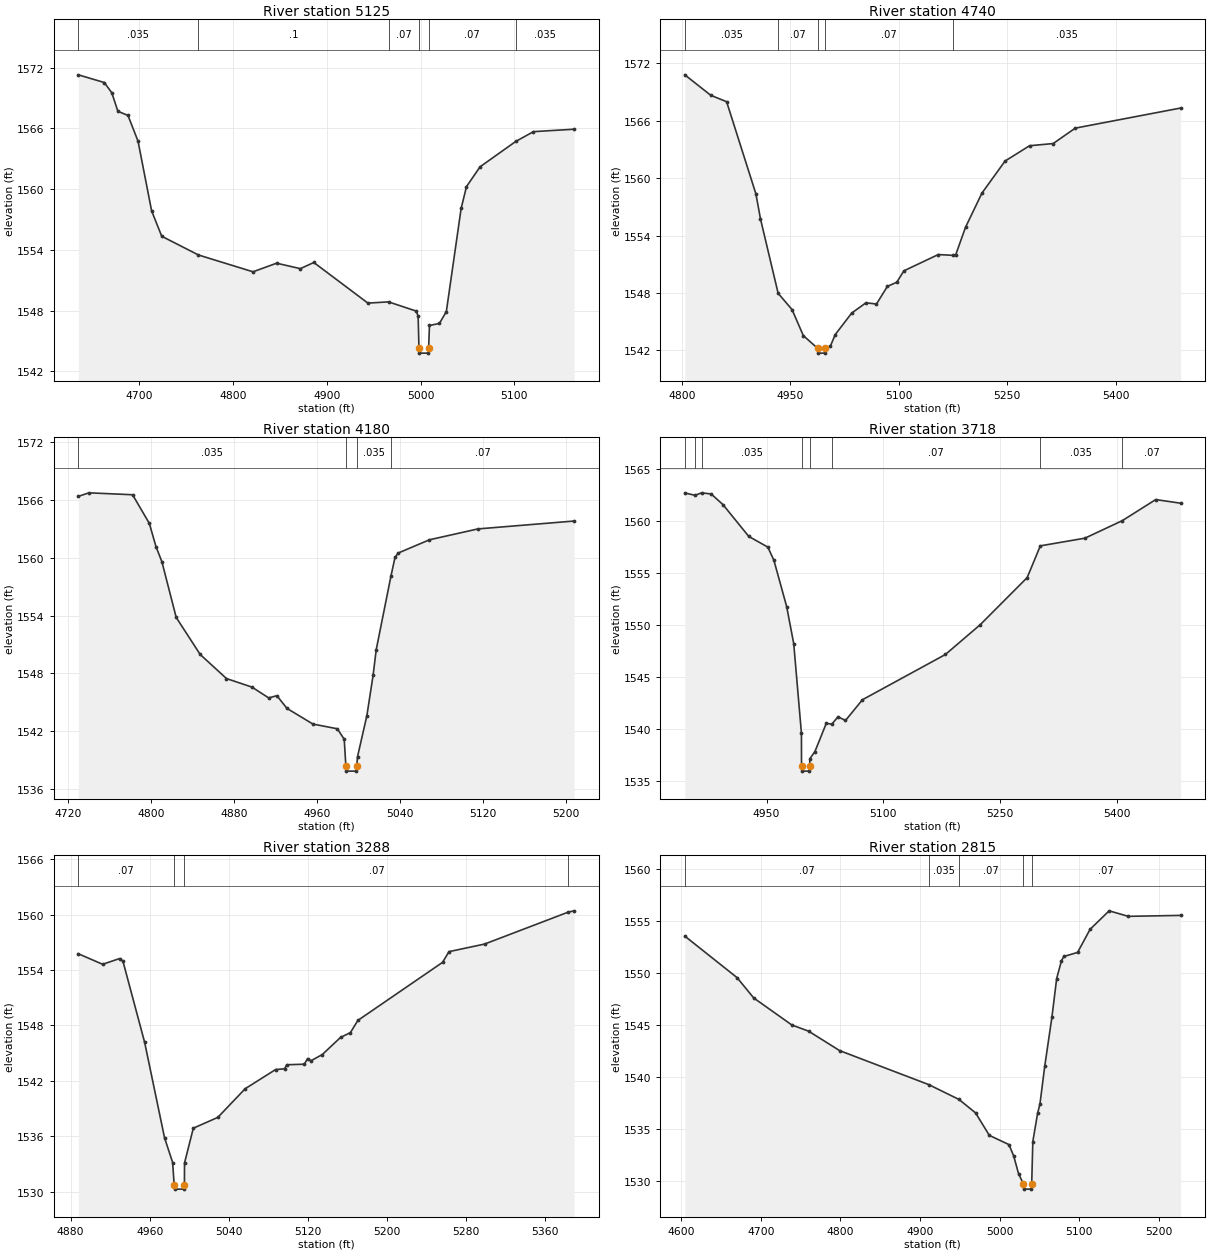
Type RM Length L Ch R = 1,5125,385,385,385
BEGIN DESCRIPTION:
Pass Creek 10.0
END DESCRIPTION:
XS GIS Cut Line= 3
      1937724.96     13893575.03      1938025.00     13893375.00
      1938193.37     13893381.40
#Sta/Elev= 30
  4634.8 1571.28  4662.5 1570.52  4670.5 1569.51  4677.0 1567.68  4687.8 1567.27
  4698.5 1564.73  4713.0 1557.85  4723.8 1555.34  4763.0 1553.49  4821.2 1551.83
  4846.4 1552.68  4871.7 1552.14  4886.1 1552.75  4943.8 1548.74  4965.8 1548.86
  4995.4 1547.95  4997.4 1547.45  4998.3 1544.30  4998.8 1543.80  5008.1 1543.80
  5008.6 1544.30  5009.5 1546.53  5020.1 1546.73  5027.5 1547.90  5043.3 1558.09
  5049.0 1560.24  5063.5 1562.20  5101.7 1564.71  5120.5 1565.67  5163.9 1565.91
#Mann=6,-1,0
  4634.8   0.035       0  4763.0     0.1       0  4965.8    0.07       0
  4998.3    0.05       0  5008.6    0.07       0  5101.7   0.035       0
Bank Sta=4998.3,5008.6
Exp/Cntr=0.3,0.1

Type RM Length L Ch R = 1,4740,560,560,560
BEGIN DESCRIPTION:
Pass Creek 9.0
END DESCRIPTION:
XS GIS Cut Line= 3
      1938014.03     13893904.16      1938068.73     13893711.94
      1938263.33     13893267.31
#Sta/Elev= 30
  4804.3 1570.79  4840.2 1568.65  4862.1 1567.98  4902.6 1558.34  4908.9 1555.73
  4933.3 1547.96  4952.5 1546.26  4968.1 1543.54  4987.9 1542.21  4988.4 1541.71
  4997.7 1541.71  4998.2 1542.21  5005.6 1542.46  5012.2 1543.65  5035.0 1545.90
  5054.7 1546.97  5069.2 1546.84  5084.2 1548.68  5097.3 1549.12  5107.1 1550.31
  5154.6 1552.01  5174.4 1551.93  5178.5 1551.95  5192.3 1554.87  5215.0 1558.44
  5246.9 1561.78  5280.7 1563.38  5313.4 1563.61  5343.9 1565.22  5489.5 1567.32
#Mann=5,-1,0
  4804.3   0.035       0  4933.3    0.07       0  4987.9    0.05       0
  4998.2    0.07       0  5174.4   0.035       0
Bank Sta=4987.9,4998.2
Exp/Cntr=0.3,0.1

Type RM Length L Ch R = 1,4180,462,462,462
BEGIN DESCRIPTION:
Pass Creek 8.0
END DESCRIPTION:
XS GIS Cut Line= 3
      1938474.99     13893825.04      1938575.00     13893575.00
      1938590.51     13893367.68
#Sta/Elev= 30
  4730.3 1566.38  4740.5 1566.75  4782.5 1566.55  4798.6 1563.58  4805.1 1561.14
  4810.7 1559.60  4824.5 1553.80  4847.6 1549.95  4872.9 1547.45  4897.4 1546.56
  4913.5 1545.44  4921.4 1545.67  4931.1 1544.35  4956.1 1542.72  4979.6 1542.23
  4986.2 1541.14  4987.8 1538.33  4988.3 1537.83  4997.7 1537.83  4998.2 1538.33
  4999.0 1539.33  5008.0 1543.59  5014.0 1547.79  5017.0 1550.45  5031.2 1558.11
  5035.1 1560.05  5038.1 1560.49  5068.2 1561.87  5114.9 1563.00  5207.5 1563.82
#Mann=4,-1,0
  4730.3   0.035       0  4987.8   0.035       0  4998.2   0.035       0
  5031.2    0.07       0
Bank Sta=4987.8,4998.2
Exp/Cntr=0.3,0.1

Type RM Length L Ch R = 1,3718,430,430,430
BEGIN DESCRIPTION:
Pass Creek 7.0
END DESCRIPTION:
XS GIS Cut Line= 3
      1939011.13     13893863.87      1938989.33     13893711.20
      1938818.14     13893259.57
#Sta/Elev= 30
  4844.9 1562.72  4858.2 1562.49  4866.4 1562.73  4878.8 1562.62  4894.0 1561.59
  4927.1 1558.53  4951.6 1557.50  4959.4 1556.23  4975.8 1551.77  4984.9 1548.19
  4994.8 1539.55  4994.9 1536.41  4995.4 1535.91  5004.8 1535.91  5005.3 1536.41
  5005.7 1537.12  5012.1 1537.79  5026.7 1540.51  5033.9 1540.44  5041.8 1541.15
  5051.4 1540.79  5073.2 1542.79  5179.8 1547.15  5224.4 1550.01  5284.9 1554.56
  5301.8 1557.62  5359.1 1558.36  5407.2 1560.05  5450.1 1562.08  5482.1 1561.73
#Mann=8,-1,0
  4844.9   0.035       0  4858.2    0.07       0  4866.4   0.035       0
  4994.9   0.035       0  5005.3   0.035       0  5033.9    0.07       0
  5301.8   0.035       0  5407.2    0.07       0
Bank Sta=4994.9,5005.3
Exp/Cntr=0.3,0.1

Type RM Length L Ch R = 1,3288,473,473,473
BEGIN DESCRIPTION:
Pass Creek 6.0
END DESCRIPTION:
XS GIS Cut Line= 3
      1939325.03     13893475.01      1939225.00     13893425.00
      1938873.68     13893256.42
#Sta/Elev= 30
  4887.8 1555.75  4912.4 1554.61  4929.5 1555.23  4932.9 1554.95  4954.9 1546.14
  4975.0 1535.82  4983.2 1533.14  4984.7 1530.76  4985.2 1530.26  4994.6 1530.26
  4995.1 1530.76  4995.2 1533.09  5004.1 1536.86  5028.9 1538.03  5056.5 1541.13
  5087.3 1543.21  5096.4 1543.29  5098.6 1543.73  5116.4 1543.79  5119.7 1544.40
  5123.1 1544.16  5134.6 1544.84  5153.0 1546.69  5163.0 1547.21  5170.5 1548.53
  5256.2 1554.82  5262.7 1555.98  5298.7 1556.80  5383.3 1560.26  5389.3 1560.40
#Mann=4,-1,0
  4887.8    0.07       0  4984.7    0.05       0  4995.1    0.07       0
  5383.3   0.035       0
Bank Sta=4984.7,4995.1
Exp/Cntr=0.3,0.1

Type RM Length L Ch R = 1,2815,480,480,480
BEGIN DESCRIPTION:
Pass Creek 5.0
END DESCRIPTION:
XS GIS Cut Line= 4
      1939425.00     13893425.00      1939425.00     13893025.00
      1939425.00     13892925.00      1939425.44     13892801.40
#Sta/Elev= 30
  4604.2 1553.56  4669.9 1549.57  4690.9 1547.61  4738.9 1545.01  4759.9 1544.42
  4798.9 1542.55  4911.0 1539.28  4949.1 1537.85  4969.9 1536.56  4987.2 1534.40
  5011.9 1533.51  5017.9 1532.41  5023.9 1530.73  5030.0 1529.73  5030.5 1529.23
  5040.0 1529.23  5040.5 1529.73  5041.9 1533.80  5047.9 1536.51  5050.9 1537.43
  5056.9 1541.05  5065.9 1545.75  5071.9 1549.48  5077.9 1551.18  5080.9 1551.60
  5098.2 1551.99  5113.9 1554.21  5137.9 1555.99  5161.9 1555.46  5227.8 1555.55
#Mann=5,-1,0
  4604.2    0.07       0  4911.0   0.035       0  4949.1    0.07       0
  5030.0    0.05       0  5040.5    0.07       0
Bank Sta=5030,5040.5
Exp/Cntr=0.3,0.1

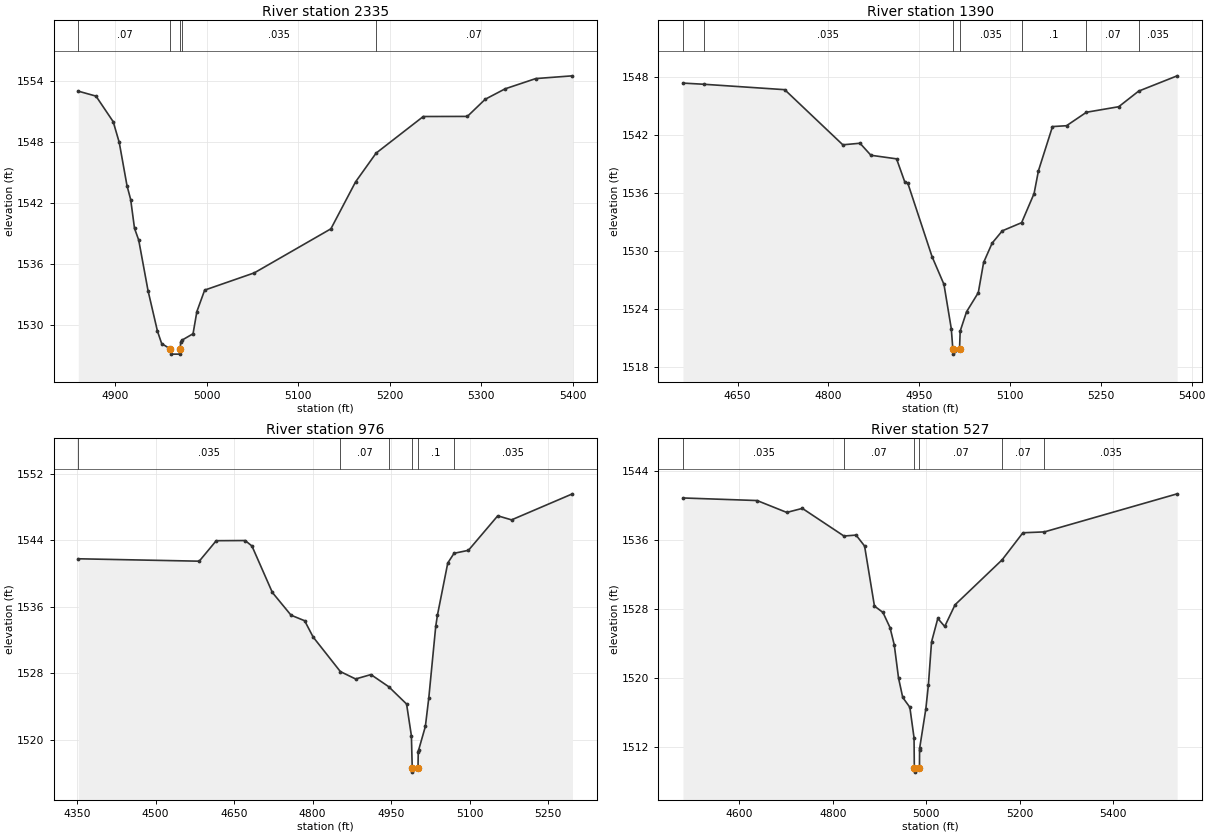
Type RM Length L Ch R = 1,2335,945,945,945
BEGIN DESCRIPTION:
Pass Creek 4.0
END DESCRIPTION:
XS GIS Cut Line= 4
      1939924.98     13893324.98      1939825.00     13893225.00
      1939725.00     13893025.00      1939657.48     13892863.23
#Sta/Elev= 30
  4859.3 1553.00  4878.7 1552.51  4897.5 1549.99  4904.1 1547.95  4912.6 1543.68
  4916.6 1542.32  4920.8 1539.48  4925.4 1538.32  4935.6 1533.33  4945.9 1529.34
  4950.5 1528.12  4960.1 1527.58  4960.6 1527.08  4970.1 1527.08  4970.6 1527.58
  4971.4 1528.32  4972.6 1528.45  4984.8 1529.09  4989.0 1531.28  4997.5 1533.39
  5051.8 1535.09  5135.5 1539.43  5162.5 1544.06  5184.9 1546.89  5236.5 1550.50
  5284.7 1550.51  5304.2 1552.20  5326.0 1553.23  5359.5 1554.24  5399.6 1554.51
#Mann=5,-1,0
  4859.3    0.07       0  4960.1   0.035       0  4970.6    0.07       0
  4972.6   0.035       0  5184.9    0.07       0
Bank Sta=4960.1,4970.6
Exp/Cntr=0.3,0.1

Type RM Length L Ch R = 1,1390,414,414,414
BEGIN DESCRIPTION:
Pass Creek 3.0
END DESCRIPTION:
XS GIS Cut Line= 3
      1940156.89     13893559.07      1940525.00     13893325.00
      1940686.73     13892980.83
#Sta/Elev= 30
  4559.6 1547.32  4594.0 1547.20  4727.7 1546.64  4823.7 1540.95  4852.1 1541.11
  4870.1 1539.87  4912.5 1539.50  4926.4 1537.06  4931.0 1537.00  4971.1 1529.41
  4990.8 1526.54  5002.9 1521.97  5005.5 1519.84  5006.0 1519.34  5016.5 1519.84
  5017.6 1521.71  5028.1 1523.71  5047.5 1525.68  5056.3 1528.80  5070.4 1530.80
  5087.2 1532.07  5119.1 1532.91  5139.7 1535.92  5146.9 1538.27  5170.1 1542.83
  5193.3 1542.92  5226.2 1544.31  5279.5 1544.88  5312.4 1546.49  5376.1 1548.07
#Mann=7,-1,0
  4559.6    0.07       0  4594.0   0.035       0  5005.5   0.035       0
  5016.5   0.035       0  5119.1     0.1       0  5226.2    0.07       0
  5312.4   0.035       0
Bank Sta=5005.5,5016.5
Exp/Cntr=0.3,0.1

Type RM Length L Ch R = 1,976,449,449,449
BEGIN DESCRIPTION:
Pass Creek 2.0
END DESCRIPTION:
XS GIS Cut Line= 3
      1940223.16     13893824.69      1940825.00     13893575.00
      1941091.83     13893454.40
#Sta/Elev= 30
  4352.2 1541.79  4583.4 1541.50  4615.9 1543.97  4671.1 1543.99  4684.1 1543.33
  4723.1 1537.73  4758.8 1534.99  4784.8 1534.32  4801.0 1532.36  4853.1 1528.19
  4882.2 1527.30  4911.5 1527.83  4945.4 1526.37  4979.6 1524.28  4988.8 1520.45
  4990.4 1516.57  4990.9 1516.07  5001.4 1516.57  5001.9 1518.47  5002.4 1518.68
  5015.5 1521.58  5022.1 1525.05  5035.3 1533.64  5038.6 1535.01  5058.3 1541.28
  5070.3 1542.45  5097.8 1542.81  5153.8 1546.97  5180.2 1546.48  5296.6 1549.62
#Mann=6,-1,0
  4352.2   0.035       0  4853.1    0.07       0  4945.4     0.1       0
  4990.4    0.05       0  5001.4     0.1       0  5070.3   0.035       0
Bank Sta=4990.4,5001.4
Exp/Cntr=0.3,0.1

Type RM Length L Ch R = 1,527,0,0,0
BEGIN DESCRIPTION:
Pass Creek 1.0
END DESCRIPTION:
XS GIS Cut Line= 4
      1940258.54     13894041.56      1940775.00     13893975.00
      1940875.00     13893925.00      1941224.22     13893683.90
#Sta/Elev= 30
  4479.6 1540.89  4638.1 1540.59  4701.6 1539.21  4734.9 1539.68  4823.9 1536.47
  4849.8 1536.58  4868.0 1535.31  4889.1 1528.34  4907.3 1527.60  4922.4 1525.84
  4931.5 1523.83  4940.6 1519.99  4949.6 1517.73  4964.8 1516.59  4973.8 1513.04
  4974.4 1509.56  4974.9 1509.06  4985.4 1509.56  4985.6 1511.61  4985.9 1511.87
  4999.0 1516.40  5004.5 1519.20  5011.2 1524.18  5024.6 1526.90  5039.4 1525.97
  5061.5 1528.49  5162.2 1533.71  5206.6 1536.85  5252.5 1536.95  5536.5 1541.37
#Mann=6,-1,0
  4479.6   0.035       0  4823.9    0.07       0  4974.4   0.035       0
  4985.4    0.07       0  5162.2    0.07       0  5252.5   0.035       0
Bank Sta=4974.4,4985.4
Exp/Cntr=0.3,0.1

Chan Stop Cuts=-1