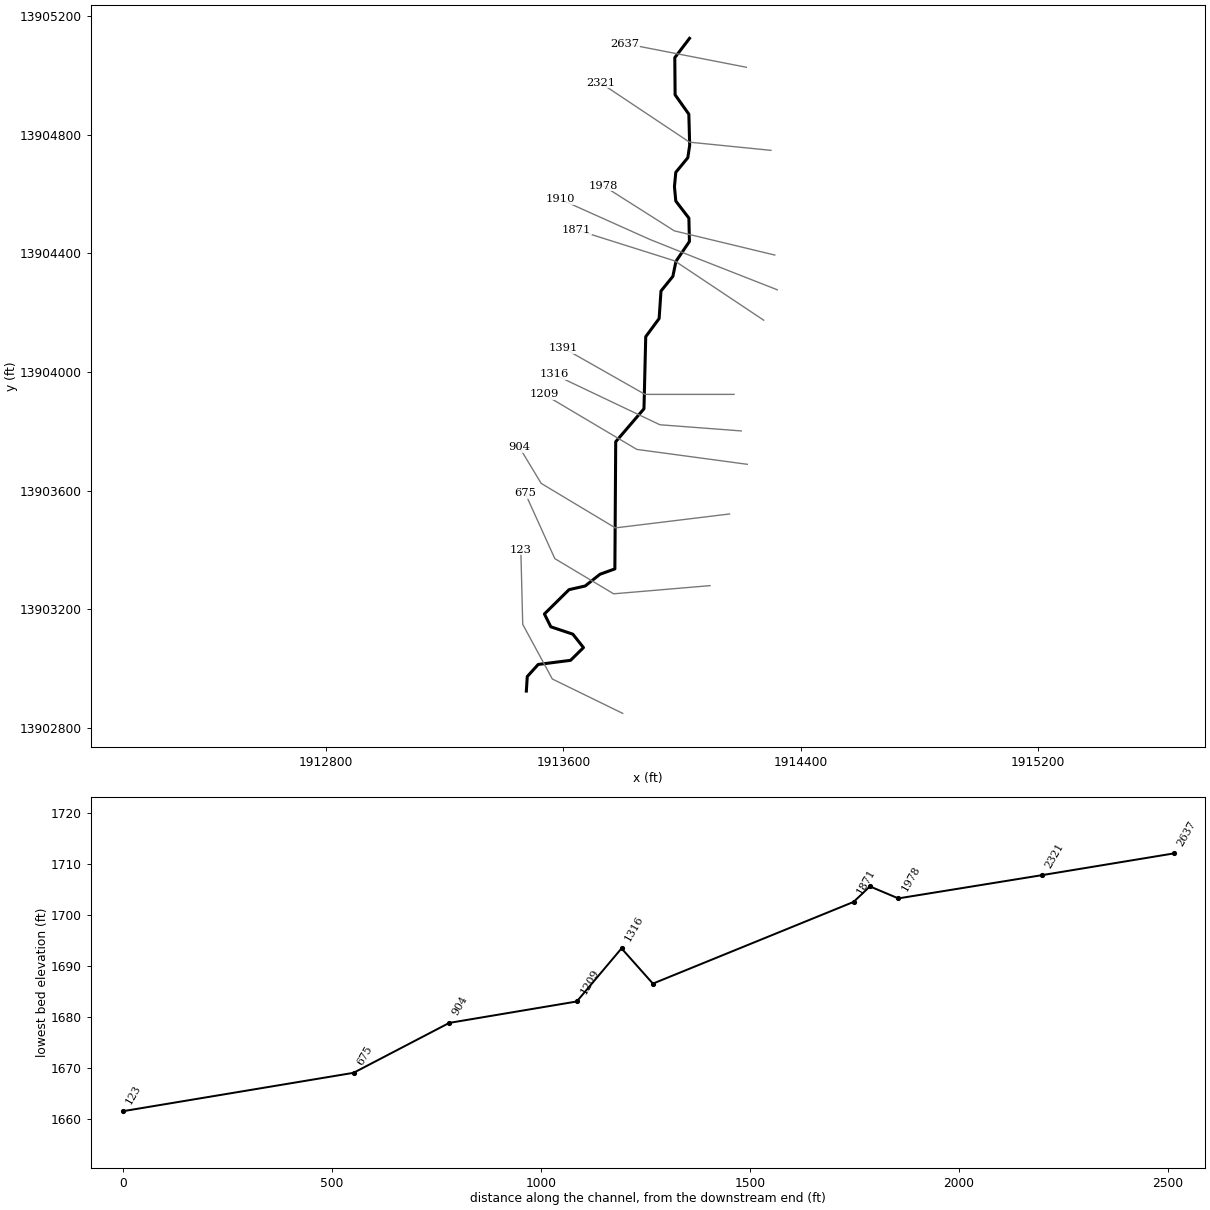
--- Peterson Creek.prj (project) ---

Proj Title=Peterson Creek Base Level Engineering
Current Plan=p01
Default Exp/Contr=0.3,0.1
English Units
Geom File=g01
Flow File=f01
Plan File=p01
Y Axis Title=Elevation
X Axis Title(PF)=Main Channel Distance
X Axis Title(XS)=Station
BEGIN DESCRIPTION:
Peterson Creek
END DESCRIPTION:
DSS Export Rating Curves= 0
DSS Export Rating Curve Sorted= 0
DSS Export Volume Flow Curves= 0
DXF OffsetX= 0
DXF OffsetY= 0
DXF ScaleX= 1
DXF ScaleY= 10

--- Peterson Creek.p01 (plan) ---

Plan Title=Multiple Run
Short Identifier=Multiple
Geom File=g01
Flow File=f01
Subcritical Flow
K Sum by GR= 0
Std Step Tol= 0.01
Critical Tol= 0.01
Num of Std Step Trials= 20
Max Error Tol= 0.3
Flow Tol Ratio= 0.001
Split Flow NTrial= 30
Split Flow Tol= 0.02
Split Flow Ratio= 0.02
Log Output Level= 0
Friction Slope Method= 1
Unsteady Friction Slope Method= 2
Unsteady Bridges Friction Slope Method= 1
Parabolic Critical Depth
Global Vel Dist=  1 , 1 , 1
Global Log Level= 0
CheckData=True
Encroach Param= -1, 0, 0, 0
BEGIN DESCRIPTION:
Multiple Run
END DESCRIPTION:

--- Peterson Creek.f01 (steady flow) ---

Flow Title=Multiple
Program Version=4.10
Number of Profiles= 7
Profile Names=10-year,25-year,50-year,1pct_min,100-year,1pct_plu,500-year
River Rch & RM=Peterson Creek,Reach-1         ,2637
     743    1239    1703    1135    2265    4520    3950
Boundary for River Rch & Prof#=Peterson Creek,Reach-1         , 1
Up Type= 0
Dn Type= 3
Dn Slope=0.01
Boundary for River Rch & Prof#=Peterson Creek,Reach-1         , 2
Up Type= 0
Dn Type= 3
Dn Slope=0.01
Boundary for River Rch & Prof#=Peterson Creek,Reach-1         , 3
Up Type= 0
Dn Type= 3
Dn Slope=0.01
Boundary for River Rch & Prof#=Peterson Creek,Reach-1         , 4
Up Type= 0
Dn Type= 3
Dn Slope=0.01
Boundary for River Rch & Prof#=Peterson Creek,Reach-1         , 5
Up Type= 0
Dn Type= 3
Dn Slope=0.01
Boundary for River Rch & Prof#=Peterson Creek,Reach-1         , 6
Up Type= 0
Dn Type= 3
Dn Slope=0.01
Boundary for River Rch & Prof#=Peterson Creek,Reach-1         , 7
Up Type= 0
Dn Type= 3
Dn Slope=0.01
DSS Import GetInterval= 0
DSS Import GetPeak= 0
DSS Import FillOption= 0

--- Peterson Creek.g01 (geometry) ---

Geom Title=Existing Conditions
Program Version=4.10

River Reach=Peterson Creek  ,Reach-1
Reach XY= 30
        1914025.       13905125.      1913975.34     13905059.84
      1913976.37     13904934.67      1914022.63     13904869.47
       1914025.5     13904764.83      1914019.26     13904722.67
      1913978.71      13904673.4      1913974.18       13904625.
      1913978.71      13904576.6      1914022.83     13904519.03
      1914024.63     13904440.27      1913979.19     13904373.27
      1913968.89     13904322.82      1913928.83     13904273.42
      1913922.53     13904180.57      1913877.38     13904119.47
      1913871.45     13903876.47      1913776.21     13903765.41
      1913773.38     13903336.81      1913723.21     13903318.73
      1913673.29     13903279.18      1913618.91     13903266.86
      1913535.89     13903184.89      1913557.42     13903141.65
      1913631.68     13903116.82       1913667.6     13903071.57
        1913624.     13903028.62      1913514.91     13903014.74
      1913478.12     13902974.01        1913475.       13902925.

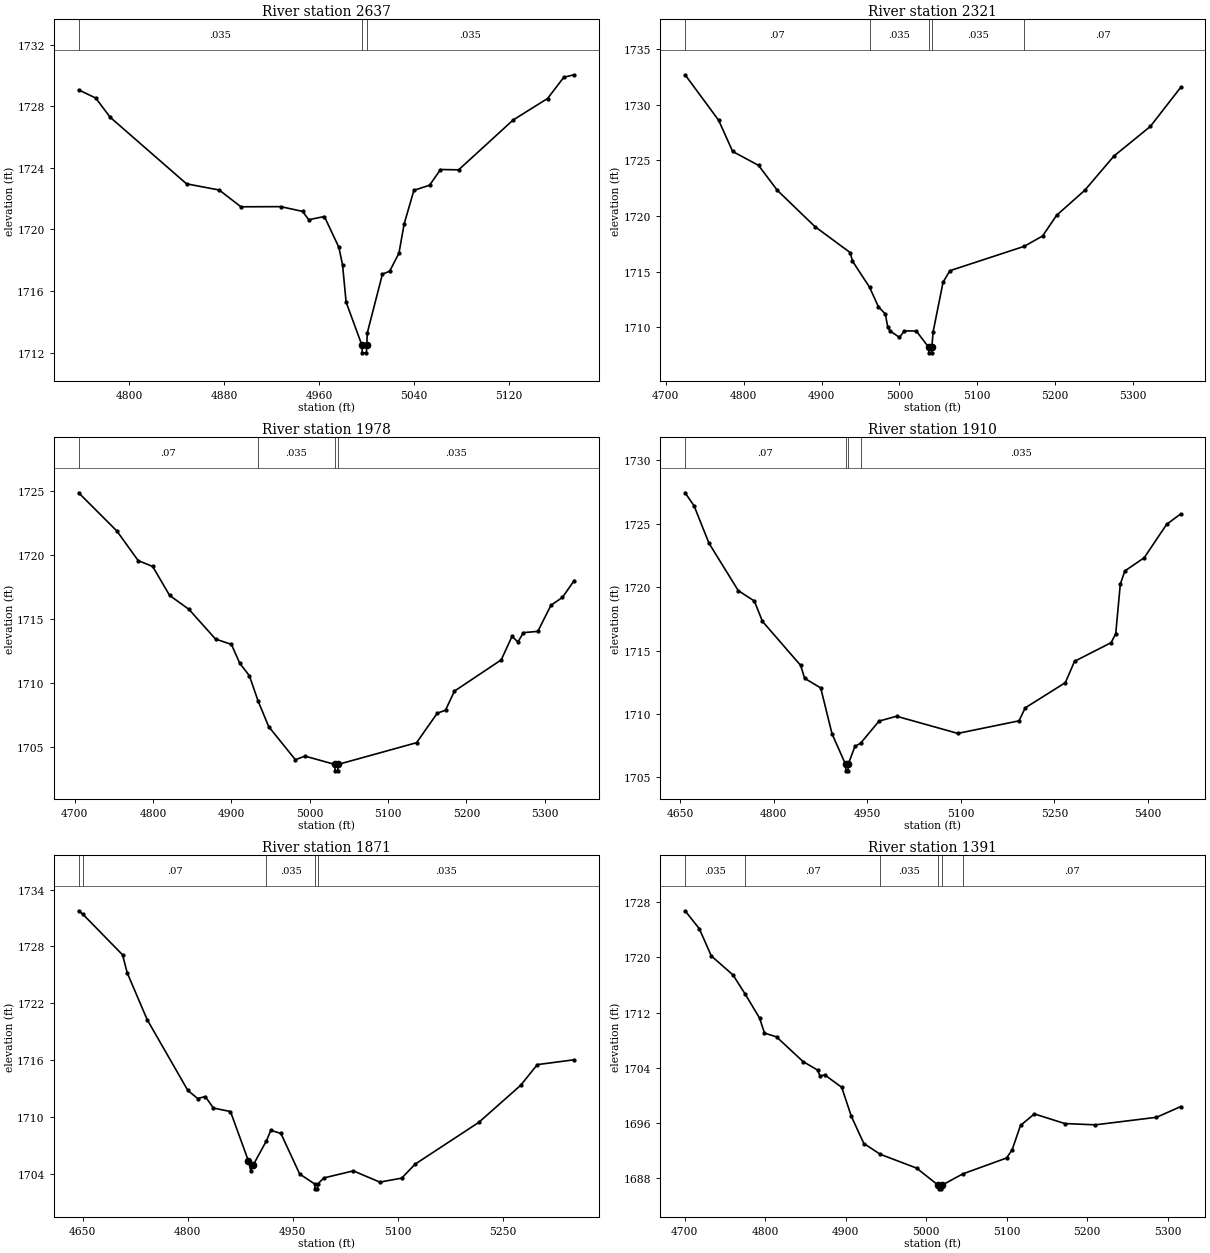
Type RM Length L Ch R = 1 ,2637    ,316,316,316
BEGIN DESCRIPTION:
Peterson Creek 6.0
END DESCRIPTION:
XS GIS Cut Line= 2
      1914216.63      13905027.5      1913806.94     13905107.35
#Sta/Elev= 30
  4757.3 1729.06  4771.7 1728.53  4783.9 1727.28  4848.2 1722.96  4875.7 1722.56
    4894 1721.47  4927.6 1721.48    4946 1721.17  4951.1 1720.63  4964.3 1720.84
  4976.5 1718.84  4979.6  1717.7  4982.6 1715.28  4995.9 1712.49  4996.2 1711.99
  4999.7 1711.99  4999.9 1712.49  5000.5  1713.3  5013.2  1717.1  5019.3 1717.29
  5027.1 1718.46  5031.5 1720.36  5039.7 1722.54  5052.9 1722.87  5062.1 1723.89
  5077.4 1723.87  5123.2  1727.1  5152.3  1728.5    5166 1729.88  5174.7 1730.04
#Mann= 3 ,-1 , 0
  4757.3    .035       0  4995.9    .035       0  4999.9    .035       0
Bank Sta=4995.9,4999.9
XS Rating Curve= 0 ,0
Exp/Cntr=0.3,0.1

Type RM Length L Ch R = 1 ,2321    ,343,343,343
BEGIN DESCRIPTION:
Peterson Creek 4.0
END DESCRIPTION:
XS GIS Cut Line= 3
       1914299.3     13904747.49        1914025.       13904775.
      1913725.02     13904974.98
#Sta/Elev= 30
  4724.8  1732.7  4767.9 1728.61  4785.9 1725.81  4819.1 1724.56  4843.2 1722.32
  4891.5 1719.06  4936.7 1716.73  4939.7 1715.96  4961.6 1713.62  4972.9 1711.87
  4981.9  1711.2  4984.9 1710.06    4988 1709.68    5000 1709.11  5006.3 1709.69
  5021.6 1709.68  5037.6 1708.22  5037.8 1707.72  5041.3 1707.72  5041.6 1708.22
  5043.2  1709.6    5056 1714.07  5064.8  1715.1  5160.3 1717.29  5183.8 1718.22
  5201.8 1720.08  5237.9 1722.32  5275.4  1725.4  5322.1 1728.06    5361 1731.56
#Mann= 5 ,-1 , 0
  4724.8     .07       0  4961.6    .035       0  5037.6    .035       0
  5041.6    .035       0  5160.3     .07       0
Bank Sta=5037.6,5041.6
XS Rating Curve= 0 ,0
Exp/Cntr=0.3,0.1

Type RM Length L Ch R = 1 ,1978    ,68,68,68
BEGIN DESCRIPTION:
Mapping XS 2f176ae1
END DESCRIPTION:
XS GIS Cut Line= 3
      1914312.34     13904394.57      1913973.82     13904476.13
      1913733.84     13904628.37
#Sta/Elev= 30
  4705.2  1724.9  4753.9 1721.92  4781.2  1719.6  4799.7 1719.14  4821.3 1716.88
    4846 1715.79  4879.9 1713.47  4900.2 1713.05  4910.8 1711.58  4923.1  1710.6
  4934.1 1708.65  4947.8 1706.62  4981.8 1704.04  4994.1 1704.32  5032.2 1703.67
  5032.5 1703.17    5036 1703.17  5036.2 1703.67  5136.5 1705.37  5162.8 1707.67
  5173.4 1707.91  5184.8  1709.4  5244.5 1711.84  5258.3 1713.68  5265.8 1713.24
  5272.9 1713.97  5291.2 1714.07    5308 1716.11  5322.7 1716.73  5337.6 1718.04
#Mann= 4 ,-1 , 0
  4705.2     .07       0  4934.1    .035       0  5032.2    .035       0
  5036.2    .035       0
Bank Sta=5032.2,5036.2
XS Rating Curve= 0 ,0
Exp/Cntr=0.3,0.1

Type RM Length L Ch R = 1 ,1910    ,39,39,39
BEGIN DESCRIPTION:
Peterson Creek 3.1
END DESCRIPTION:
XS GIS Cut Line= 4
      1914320.78     13904277.51      1914046.51     13904385.14
      1913890.26     13904447.64      1913588.15     13904583.07
#Sta/Elev= 30
  4658.2 1727.43  4672.5 1726.41  4696.5 1723.45  4743.4 1719.72  4769.2  1718.9
  4782.1  1717.3  4843.3 1713.83  4849.8 1712.81  4875.5 1712.05  4893.6 1708.44
  4915.4 1706.02  4915.7 1705.52  4919.2 1705.52  4919.4 1706.02  4930.3 1707.44
  4939.4  1707.7    4969 1709.44  4997.1 1709.82  5095.1 1708.47  5193.2 1709.46
  5203.1 1710.48  5267.5 1712.47  5282.2 1714.15  5340.8 1715.62  5348.2 1716.33
  5355.5 1720.22  5362.8 1721.27  5393.8 1722.31  5429.9 1724.95  5452.2 1725.76
#Mann= 4 ,-1 , 0
  4658.2     .07       0  4915.4    .035       0  4919.4     .07       0
  4939.4    .035       0
Bank Sta=4915.4,4919.4
XS Rating Curve= 0 ,0
Exp/Cntr=0.3,0.1

Type RM Length L Ch R = 1 ,1871    ,480,480,480
BEGIN DESCRIPTION:
Peterson Creek 3.0
END DESCRIPTION:
XS GIS Cut Line= 3
      1914275.02     13904174.99        1913975.       13904375.
      1913643.52      13904479.7
#Sta/Elev= 30
  4644.1 1731.76  4650.1  1731.4  4706.9 1727.12  4713.5 1725.23  4742.1 1720.29
  4800.1 1712.85  4814.2 1711.99  4825.1  1712.2  4836.7 1710.99  4861.1 1710.62
  4886.6 1705.45    4890 1704.41  4893.6 1704.99  4912.5 1707.54  4918.8 1708.64
  4933.2 1708.31    4960 1704.04  4981.7 1702.98  4981.9 1702.48  4985.4 1702.48
  4985.7 1702.98  4994.6 1703.63  5036.7 1704.37  5074.5 1703.19  5105.9 1703.61
  5124.8 1705.07    5216 1709.48  5275.8 1713.38  5299.6 1715.56  5352.3 1716.07
#Mann= 5 ,-1 , 0
  4644.1    .035       0  4650.1     .07       0  4912.5    .035       0
  4981.7    .035       0  4985.7    .035       0
#Block Obstruct= 2 , 0
                         4946.85         1704.33
Bank Sta=4886.6,4893.6
XS Rating Curve= 0 ,0
Exp/Cntr=0.3,0.1

Type RM Length L Ch R = 1 ,1391    ,75,75,75
BEGIN DESCRIPTION:
Peterson Creek 2.0
END DESCRIPTION:
XS GIS Cut Line= 3
      1914175.03       13903925.        1913875.       13903925.
       1913600.4      13904080.9
#Sta/Elev= 30
  4700.4 1726.77    4718 1724.18    4733 1720.22    4760 1717.46  4775.3 1714.65
    4793  1711.2    4799 1709.04    4814 1708.49    4847 1704.91    4865 1703.68
    4868 1702.83    4874 1702.97    4895 1701.18    4907 1696.97  4922.5 1693.03
  4942.9 1691.47    4988 1689.47  5015.2 1686.96  5015.4 1686.46  5018.9 1686.46
  5019.2 1686.96  5045.3 1688.62  5099.9 1690.93  5106.8 1692.12  5117.2 1695.65
  5134.4 1697.32  5172.4 1695.92  5210.3 1695.74  5286.2 1696.83  5316.2 1698.38
#Mann= 6 ,-1 , 0
  4700.4    .035       0  4775.3     .07       0  4942.9    .035       0
  5015.2    .035       0  5019.2    .035       0  5045.3     .07       0
Bank Sta=5015.2,5019.2
XS Rating Curve= 0 ,0
Exp/Cntr=0.3,0.1

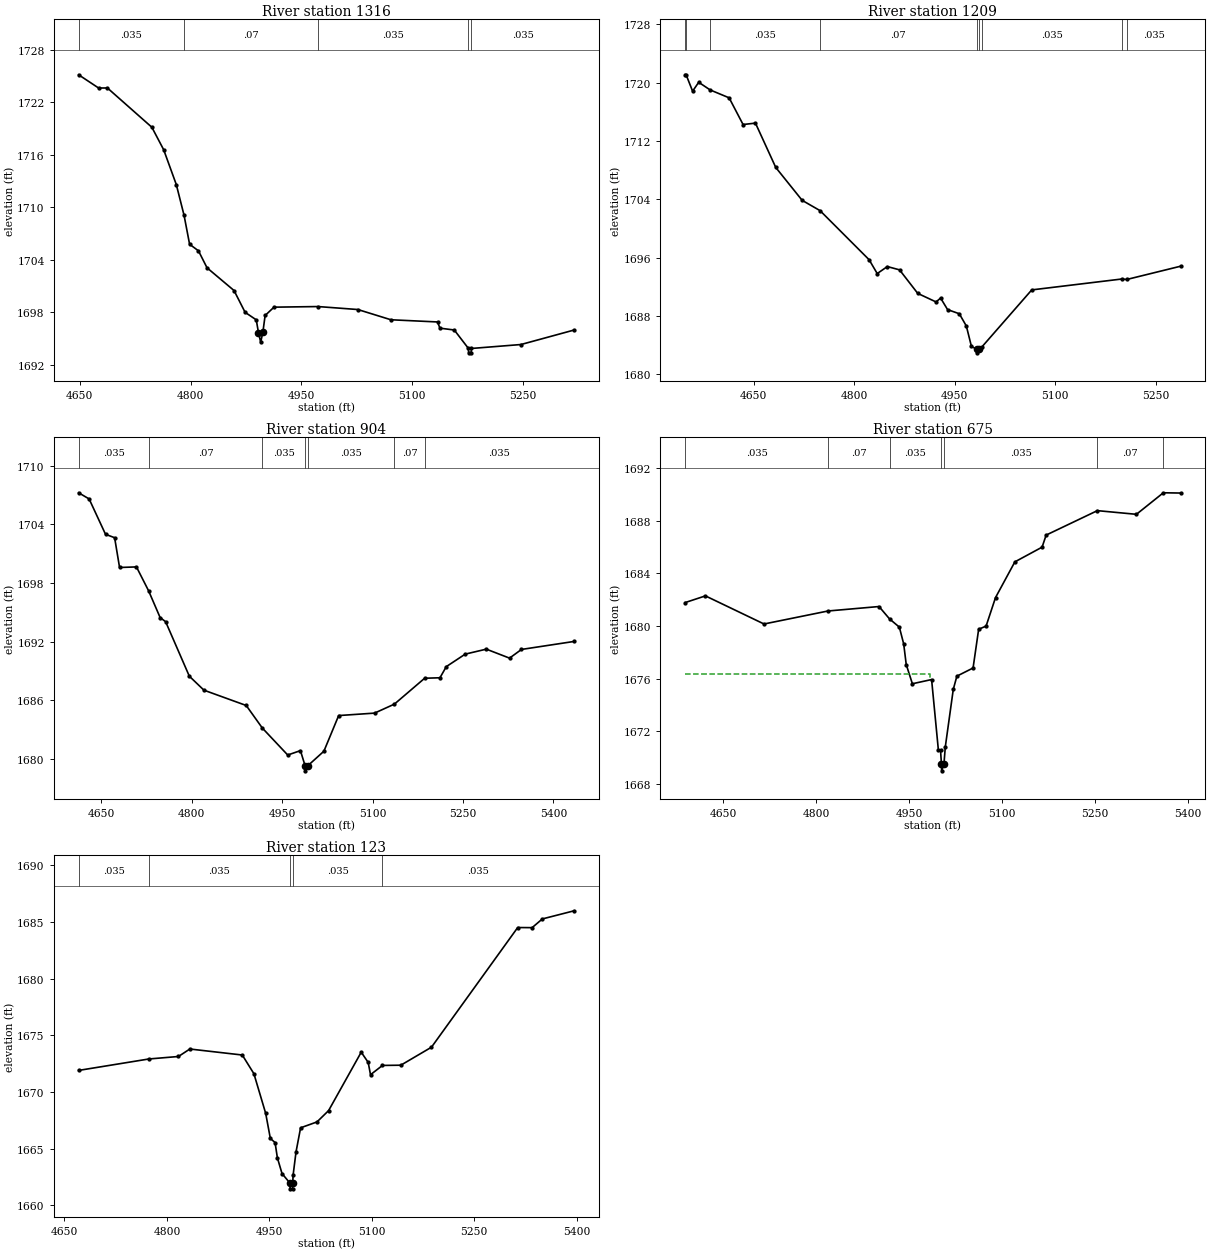
Type RM Length L Ch R = 1 ,1316    ,107,107,107
BEGIN DESCRIPTION:
Peterson Creek 1.1
END DESCRIPTION:
XS GIS Cut Line= 3
      1914199.33      13903801.8      1913924.98     13903822.64
      1913567.33     13903992.78
#Sta/Elev= 30
  4648.4 1725.15  4675.4 1723.64  4687.4 1723.64  4747.6 1719.15  4763.6 1716.58
  4780.7  1712.6  4791.2 1709.09  4798.7 1705.78  4810.7 1705.03  4822.3 1703.09
  4858.9 1700.49  4873.9    1698    4889 1697.14    4892 1695.67    4895 1694.58
    4898 1695.76    4901 1697.64    4913 1698.59  4972.6 1698.66  5026.6 1698.32
  5071.4 1697.15  5134.5  1696.9  5137.8 1696.19  5157.2 1695.98  5176.4 1693.87
  5176.6 1693.37  5180.1 1693.37  5180.4 1693.87  5247.5 1694.32  5319.6 1695.98
#Mann= 5 ,-1 , 0
  4648.4    .035       0  4791.2     .07       0  4972.6    .035       0
  5176.4    .035       0  5180.4    .035       0
#Block Obstruct= 2 , 0
                         5034.77          1697.9
Bank Sta=4892,4898
XS Rating Curve= 0 ,0
Exp/Cntr=0.3,0.1

Type RM Length L Ch R = 1 ,1209    ,305,305,305
BEGIN DESCRIPTION:
Mapping XS ffceb72b
END DESCRIPTION:
XS GIS Cut Line= 3
      1914219.57     13903689.34      1913847.42     13903739.52
      1913534.39     13903925.25
#Sta/Elev= 30
  4547.6 1721.09  4549.5    1721  4558.8 1718.84  4567.9 1720.06    4585 1719.01
  4613.3 1717.93  4634.1 1714.27  4652.6 1714.46  4682.9 1708.38  4722.3 1703.87
    4749 1702.46  4822.2 1695.73  4834.3 1693.83  4849.4 1694.79  4867.6 1694.34
  4894.8 1691.11  4922.1 1689.94  4928.9 1690.47  4939.3 1688.89  4956.8 1688.32
  4967.3 1686.64  4974.9 1683.84  4982.7 1683.46  4982.9 1682.96  4986.7 1683.46
  4990.5 1683.77  5064.9 1691.59  5198.9 1693.08  5206.7 1693.02  5287.1 1694.84
#Mann= 9 ,-1 , 0
  4547.6    .035       0  4549.5     .07       0    4585    .035       0
    4749     .07       0  4982.7    .035       0  4986.7     .07       0
  4990.5    .035       0  5198.9     .07       0  5206.7    .035       0
Bank Sta=4982.7,4986.7
XS Rating Curve= 0 ,0
Exp/Cntr=0.3,0.1

Type RM Length L Ch R = 1 ,904     ,229,229,229
BEGIN DESCRIPTION:
Peterson Creek 1.0
END DESCRIPTION:
XS GIS Cut Line= 4
       1914159.7     13903521.89        1913775.       13903475.
        1913525.       13903625.      1913451.23     13903747.27
#Sta/Elev= 30
  4612.5 1707.23  4629.9  1706.6  4657.1 1702.98  4672.2 1702.63  4680.4 1699.58
  4708.4 1699.64  4728.5  1697.2  4747.7 1694.45  4756.8 1694.03  4796.1 1688.45
  4820.3 1687.02  4890.5 1685.45  4917.2 1683.14  4959.3 1680.38  4980.4 1680.83
  4988.2 1679.26  4988.5 1678.76  4992.2 1679.26  5019.3 1680.77  5043.8 1684.42
  5103.3 1684.67  5136.2 1685.59  5186.4 1688.24  5211.8 1688.29  5222.3 1689.43
  5253.7 1690.71  5288.7 1691.22  5327.2  1690.3    5347 1691.19  5434.4 1692.01
#Mann= 7 ,-1 , 0
  4612.5    .035       0  4728.5     .07       0  4917.2    .035       0
  4988.2    .035       0  4992.2    .035       0  5136.2     .07       0
  5186.4    .035       0
Bank Sta=4988.2,4992.2
XS Rating Curve= 0 ,0
Exp/Cntr=0.3,0.1

Type RM Length L Ch R = 1 ,675     ,552,552,552
BEGIN DESCRIPTION:
Mapping XS f783274a
END DESCRIPTION:
XS GIS Cut Line= 4
      1914094.12     13903280.42       1913769.2     13903252.81
      1913570.96     13903371.46      1913471.04     13903592.06
#Sta/Elev= 30
    4589 1681.78  4621.8 1682.29  4716.3 1680.15  4819.5 1681.14  4901.8 1681.48
  4918.7 1680.54  4934.6 1679.91  4941.6 1678.63  4945.7 1677.06  4955.6  1675.6
  4986.6 1675.92  4997.5 1670.57    5001 1670.56  5002.5 1669.47  5002.8 1668.97
  5006.5 1669.47  5008.7 1670.79  5021.6 1675.18  5027.4 1676.18  5053.5  1676.8
  5062.5 1679.75  5074.5 1679.99  5089.7 1682.16  5120.9 1684.88  5164.8    1686
  5171.4 1686.92    5254 1688.78    5317  1688.5  5360.4 1690.14  5388.3 1690.12
#Mann= 7 ,-1 , 0
    4589    .035       0  4819.5     .07       0  4918.7    .035       0
  5002.5    .035       0  5006.5    .035       0    5254     .07       0
  5360.4    .035       0
#XS Ineff= 2 , 0
         4983.42 1676.32
Permanent Ineff=
       F       F
Bank Sta=5002.5,5006.5
XS Rating Curve= 0 ,0
Exp/Cntr=0.3,0.1

Type RM Length L Ch R = 1 ,123     ,0,0,0
BEGIN DESCRIPTION:
Peterson Creek 0.0
END DESCRIPTION:
XS GIS Cut Line= 4
       1913799.8     13902849.85      1913562.56     13902965.72
      1913462.83     13903149.88      1913456.38     13903402.14
#Sta/Elev= 30
  4670.7  1671.9  4773.6 1672.91  4816.9 1673.13  4833.6 1673.79  4910.4 1673.26
  4927.4 1671.61  4944.7  1668.1  4951.5 1665.89  4958.4 1665.53  4961.8 1664.18
  4968.6 1662.79  4980.3 1661.94  4980.5 1661.44    4984 1661.44  4984.3 1661.94
  4984.8 1662.63  4989.1  1664.7  4995.8 1666.83  5019.8 1667.35  5036.8 1668.35
  5084.6 1673.51  5094.8 1672.61  5098.2 1671.52  5115.7 1672.34  5142.6 1672.36
  5187.5 1673.95  5313.8 1684.52  5334.9 1684.51  5349.9 1685.28  5396.5    1686
#Mann= 5 ,-1 , 0
  4670.7    .035       0  4773.6    .035       0  4980.3    .035       0
  4984.3    .035       0  5115.7    .035       0
Bank Sta=4980.3,4984.3
XS Rating Curve= 0 ,0
Exp/Cntr=0.3,0.1

Chan Stop Cuts=-1
Use User Specified Reach Order=0
Composite Channel Slope=5