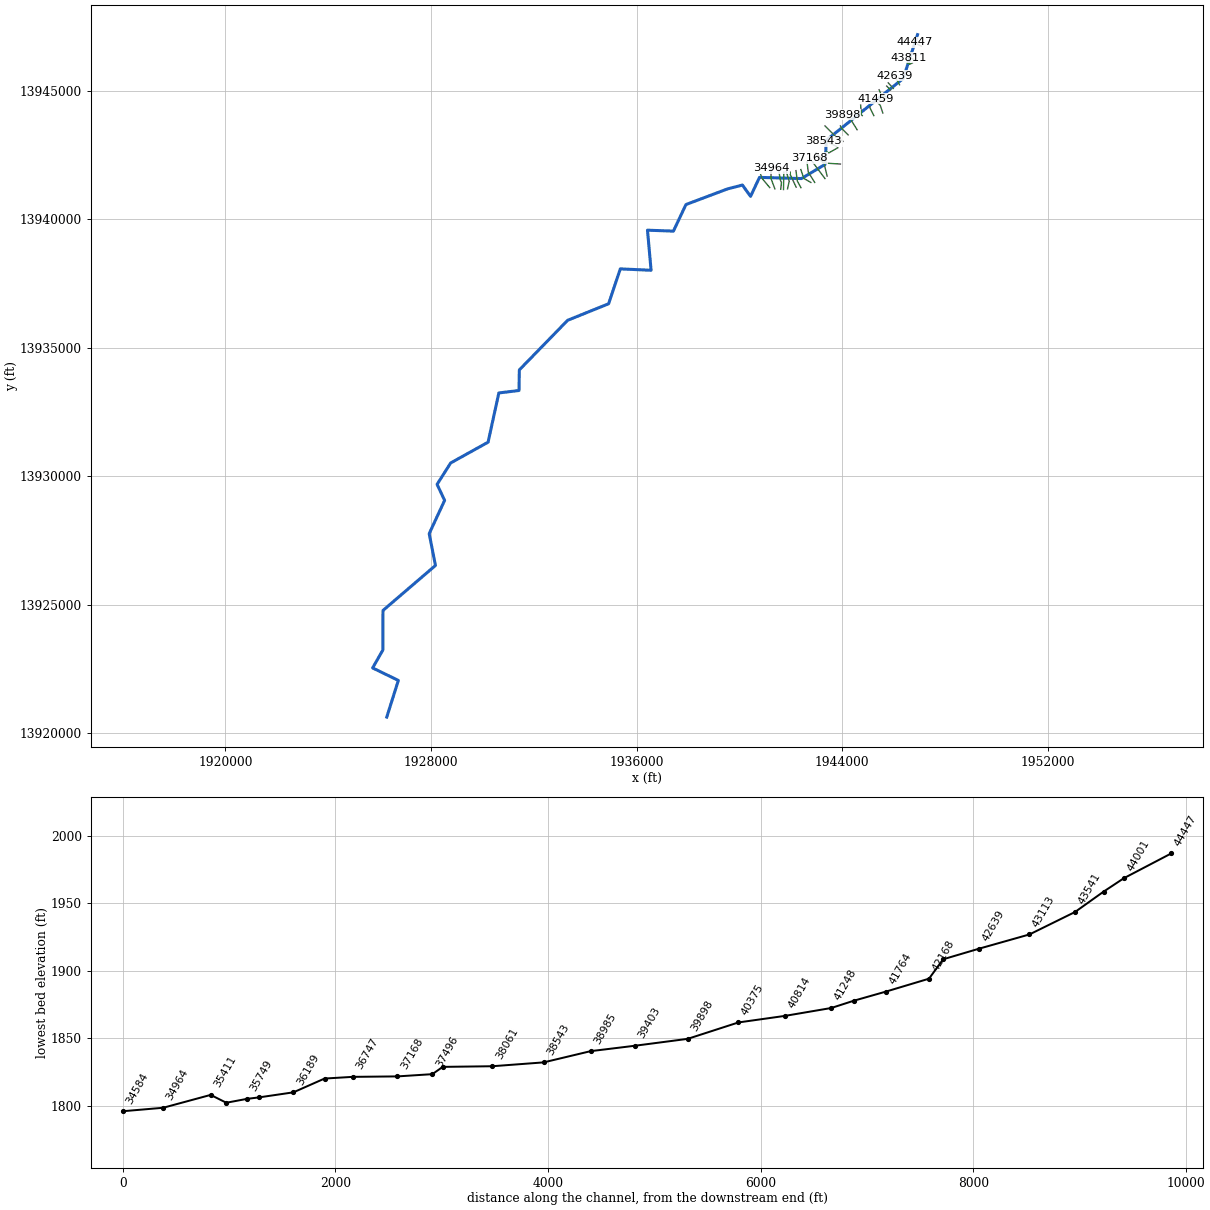
--- Quinlan Creek.prj (project) ---

Proj Title=Quinlan Creek Base Level Engineering
Current Plan=p01
Default Exp/Contr=0.3,0.1
English Units
Geom File=g01
Flow File=f01
Plan File=p01
Y Axis Title=Elevation
X Axis Title(PF)=Main Channel Distance
X Axis Title(XS)=Station
BEGIN DESCRIPTION:
Quinlan Creek
END DESCRIPTION:
DSS Export Rating Curves= 0
DSS Export Rating Curve Sorted= 0
DSS Export Volume Flow Curves= 0
DXF OffsetX= 0
DXF OffsetY= 0
DXF ScaleX= 1
DXF ScaleY= 10

--- Quinlan Creek.p01 (plan) ---

Plan Title=Multiple Run
Short Identifier=Multiple
Geom File=g01
Flow File=f01
Subcritical Flow
K Sum by GR= 0
Std Step Tol= 0.01
Critical Tol= 0.01
Num of Std Step Trials= 20
Max Error Tol= 0.3
Flow Tol Ratio= 0.001
Split Flow NTrial= 30
Split Flow Tol= 0.02
Split Flow Ratio= 0.02
Log Output Level= 0
Friction Slope Method= 1
Unsteady Friction Slope Method= 2
Unsteady Bridges Friction Slope Method= 1
Parabolic Critical Depth
Global Vel Dist=  1 , 1 , 1
Global Log Level= 0
CheckData=True
Encroach Param= -1, 0, 0, 0
BEGIN DESCRIPTION:
Multiple Run
END DESCRIPTION:

--- Quinlan Creek.f01 (steady flow) ---

Flow Title=Multiple
Number of Profiles=7
Profile Names=10-year,25-year,50-year,1pct_min,100-year,1pct_plu,500-year
River Rch & RM= Quinlan Creek,Reach-1,44447
     167     249     317     197     393     785     593
River Rch & RM= Quinlan Creek,Reach-1,44001
     605     996    1358     898    1792    3576    3075
River Rch & RM= Quinlan Creek,Reach-1,41248
    1234    2127    2989    2032    4054    8089    7362
River Rch & RM= Quinlan Creek,Reach-1,39898
    1923    3397    4849    3342    6669   13306   12464
River Rch & RM= Quinlan Creek,Reach-1,37496
    2355    4185    5996    4143    8267   16495   15532
River Rch & RM= Quinlan Creek,Reach-1,31878
    2913    5221    7522    5222   10418   20788   19762
River Rch & RM= Quinlan Creek,Reach-1,27583
    5661   10447   15351   10846   21640   43178   42534
River Rch & RM= Quinlan Creek,Reach-1,24209
    5675   10457   15348   10831   21610   43118   42372
River Rch & RM= Quinlan Creek,Reach-1,21256
    5897   10874   15968   11271   22490   44873   44124
River Rch & RM= Quinlan Creek,Reach-1,19602
    6273   11591   17043   12044   24030   47947   47250
River Rch & RM= Quinlan Creek,Reach-1,18040
    6464   11929   17524   12369   24680   49242   48414
River Rch & RM= Quinlan Creek,Reach-1,13334
    6841   12638   18581   13122   26183   52241   51420
River Rch & RM= Quinlan Creek,Reach-1,10648
    6944   12788   18757   13213   26363   52601   51505
Boundary for River Rch & Prof#=Quinlan Creek,Reach-1,1
Up Type=0
Dn Type=3
Dn Slope=0.005
Boundary for River Rch & Prof#=Quinlan Creek,Reach-1,2
Up Type=0
Dn Type=3
Dn Slope=0.005
Boundary for River Rch & Prof#=Quinlan Creek,Reach-1,3
Up Type=0
Dn Type=3
Dn Slope=0.005
Boundary for River Rch & Prof#=Quinlan Creek,Reach-1,4
Up Type=0
Dn Type=3
Dn Slope=0.005
Boundary for River Rch & Prof#=Quinlan Creek,Reach-1,5
Up Type=0
Dn Type=3
Dn Slope=0.005
Boundary for River Rch & Prof#=Quinlan Creek,Reach-1,6
Up Type=0
Dn Type=3
Dn Slope=0.005
Boundary for River Rch & Prof#=Quinlan Creek,Reach-1,7
Up Type=0
Dn Type=3
Dn Slope=0.005

--- Quinlan Creek.g01 (geometry) ---

Geom Title=Existing Conditions
Program Version=4.10

River Reach=Quinlan Creek   ,Reach-1
Reach XY= 30
        1946925.       13947175.      1946367.14     13945468.83
      1943380.17     13943069.59        1943325.       13942125.
      1942409.17     13941575.66      1940776.65     13941621.84
      1940428.22     13940882.83      1940112.87     13941323.53
      1939526.65     13941171.84      1937915.18     13940564.53
       1937427.3     13939530.83      1936418.79      13939567.2
      1936558.56     13938008.21      1935361.37     13938061.54
      1934905.28     13936704.57      1933311.76     13936061.38
      1931432.81     13934131.19      1931419.56     13933330.25
      1930635.62     13933235.05      1930216.87     13931318.93
      1928761.79     13930511.37      1928232.75     13929678.02
       1928525.6     13929054.95      1927925.52     13927759.78
      1928169.53     13926522.55      1926128.54     13924773.54
      1926123.78      13923235.5      1925726.03     13922535.43
       1926725.5     13922050.04        1926275.       13920625.

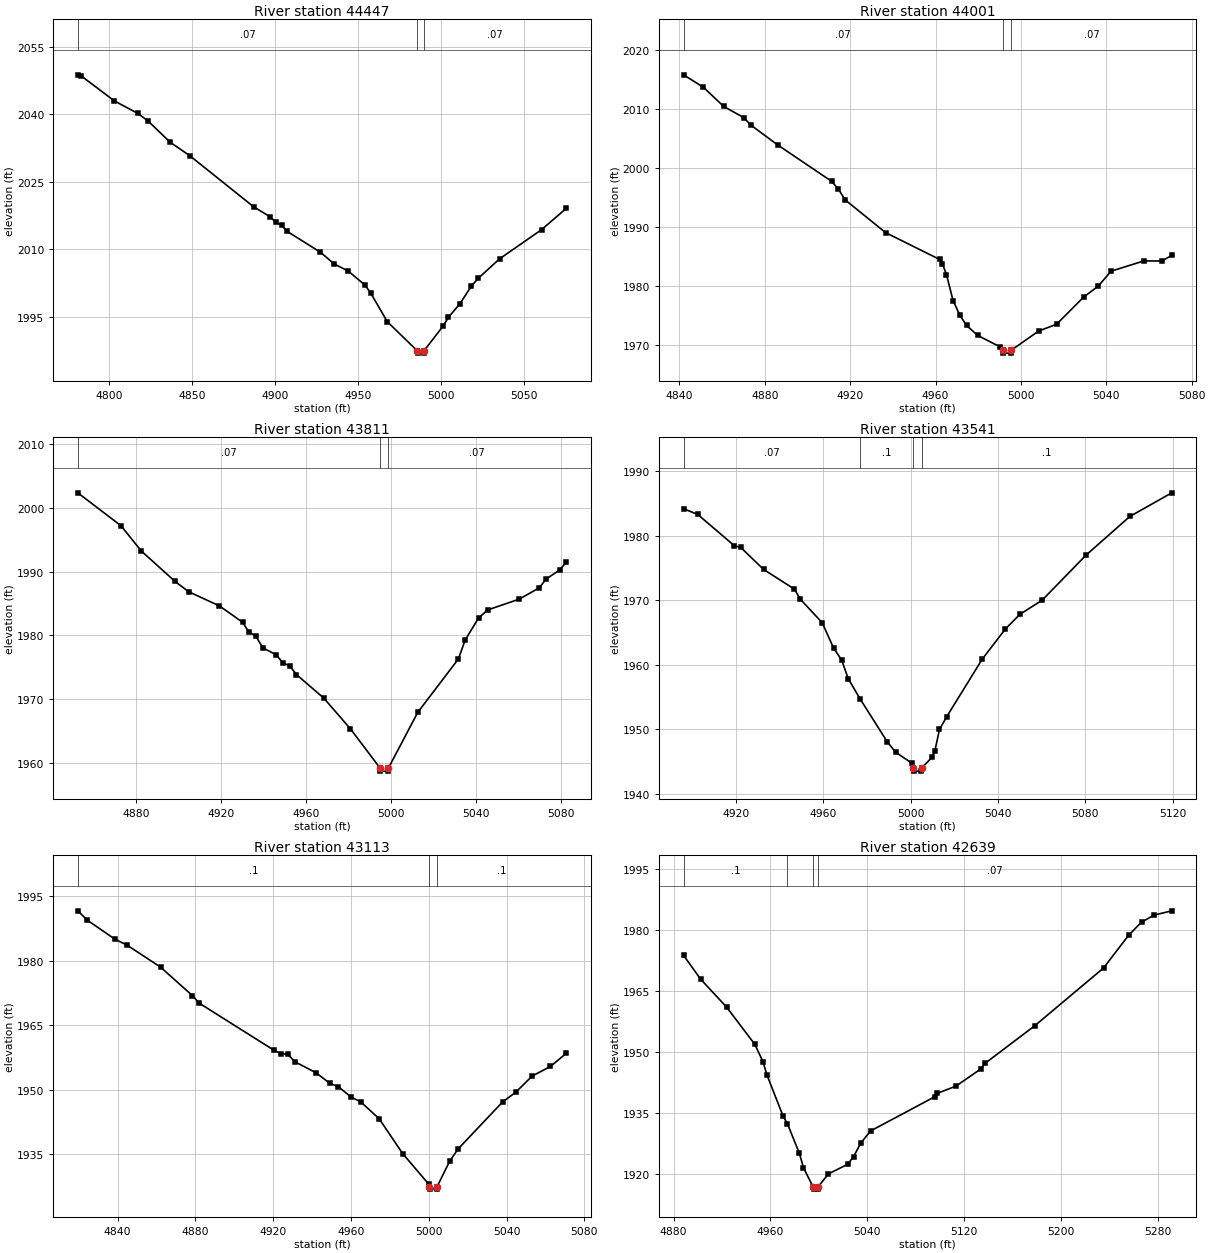
Type RM Length L Ch R = 1 ,44447   ,446,446,446
BEGIN DESCRIPTION:
Quinlan Creek 85.0
END DESCRIPTION:
XS GIS Cut Line= 3
      1947074.96     13946725.02        1946875.       13946825.
      1946824.98     13946875.02
#Sta/Elev= 30
    4781 2048.74    4783 2048.51  4803.1 2042.93  4817.1 2040.19  4823.3  2038.5
  4836.7 2033.76  4848.4 2030.81    4887 2019.44    4897 2017.21  4900.4 2015.99
  4903.8 2015.36  4907.1 2014.01  4927.2 2009.37  4935.6 2006.74    4944 2005.18
  4954.1 2002.06  4957.4 2000.37  4967.5 1993.96  4985.6 1987.47  4985.9 1986.97
  4989.4 1986.97  4989.6 1987.47    5001 1992.91  5004.4 1994.93  5011.3 1997.94
  5018.2 2001.86  5022.4  2003.6  5035.2  2007.9  5060.6  2014.4  5075.3 2019.08
#Mann= 3 ,-1 , 0
    4781     .07       0  4985.6     .05       0  4989.6     .07       0
Bank Sta=4985.6,4989.6
XS Rating Curve= 0 ,0
Exp/Cntr=0.3,0.1

Type RM Length L Ch R = 1 ,44001   ,190,190,190
BEGIN DESCRIPTION:
Quinlan Creek 84.0
END DESCRIPTION:
XS GIS Cut Line= 3
        1946875.       13946375.        1946725.       13946425.
      1946675.02     13946474.98
#Sta/Elev= 30
  4841.9 2015.73  4851.2 2013.63  4860.7 2010.38  4870.2 2008.47  4873.3 2007.26
    4886 2003.86  4911.3 1997.69  4914.5 1996.36  4917.6 1994.56  4936.6    1989
  4961.9 1984.46  4963.2 1983.76  4965.1  1981.9  4968.2  1977.5  4971.4    1975
  4974.5 1973.28  4979.8 1971.58  4990.4 1969.62  4991.5 1969.09  4991.8 1968.59
  4995.3 1968.59  4995.5 1969.09  5008.3 1972.33  5016.7 1973.48  5029.5 1978.12
  5036.3 1979.96  5042.2 1982.46  5057.5  1984.2    5066  1984.2  5070.7 1985.14
#Mann= 3 ,-1 , 0
  4841.9     .07       0  4991.5     .05       0  4995.5     .07       0
Bank Sta=4991.5,4995.5
XS Rating Curve= 0 ,0
Exp/Cntr=0.3,0.1

Type RM Length L Ch R = 1 ,43811   ,270,270,270
BEGIN DESCRIPTION:
Quinlan Creek 83.1
END DESCRIPTION:
XS GIS Cut Line= 2
      1946795.39     13946208.53      1946578.26     13946283.78
#Sta/Elev= 30
  4852.7  2002.4    4873 1997.23  4882.6 1993.25  4898.4 1988.49  4904.9 1986.85
  4919.3 1984.64  4930.2 1982.07  4933.1 1980.58  4936.5 1979.87  4939.7 1978.06
  4946.1 1976.94  4949.2 1975.68  4952.4 1975.21  4955.6 1973.84  4968.5 1970.13
    4981 1965.31  4994.9 1959.17  4995.1 1958.67  4998.6 1958.67  4998.9 1959.17
  5012.7 1967.92  5031.8 1976.29    5035 1979.28  5041.3 1982.74  5045.6    1984
  5060.4 1985.69  5069.8 1987.46  5073.1 1988.85  5079.4 1990.26  5082.5 1991.47
#Mann= 3 ,-1 , 0
  4852.7     .07       0  4994.9     .05       0  4998.9     .07       0
Bank Sta=4994.9,4998.9
XS Rating Curve= 0 ,0
Exp/Cntr=0.3,0.1

Type RM Length L Ch R = 1 ,43541   ,428,428,428
BEGIN DESCRIPTION:
Quinlan Creek 83.0
END DESCRIPTION:
XS GIS Cut Line= 3
      1946724.99       13946075.        1946625.       13946025.
        1946525.       13946075.
#Sta/Elev= 30
    4896 1984.21  4902.5 1983.32  4919.3 1978.46  4922.2  1978.2  4932.7 1974.78
  4946.8 1971.73  4949.5 1970.17  4959.5 1966.53  4964.7 1962.61  4968.4 1960.76
  4971.4 1957.87  4976.8 1954.74  4989.3 1948.06  4993.1 1946.45  5000.5 1944.76
  5001.1 1944.01  5001.4 1943.51  5004.9 1943.51  5005.1 1944.01  5009.8 1945.66
  5011.1 1946.64  5013.2 1949.97  5016.5 1951.94  5032.8 1960.88  5043.4 1965.56
  5050.1 1967.84  5060.2 1970.01  5080.3    1977  5100.4 1983.01  5119.6 1986.67
#Mann= 4 ,-1 , 0
    4896     .07       0  4976.8      .1       0  5001.1     .05       0
  5005.1      .1       0
Bank Sta=5001.1,5005.1
XS Rating Curve= 0 ,0
Exp/Cntr=0.3,0.1

Type RM Length L Ch R = 1 ,43113   ,474,474,474
BEGIN DESCRIPTION:
Quinlan Creek 82.0
END DESCRIPTION:
XS GIS Cut Line= 3
      1946575.04     13945574.97        1946425.       13945675.
      1946375.03     13945724.97
#Sta/Elev= 30
  4819.6 1991.63  4824.4 1989.48  4838.7 1985.02  4844.7 1983.71  4862.2 1978.51
  4878.5  1971.9    4882 1970.15  4920.4 1959.21    4924 1958.41  4927.6 1958.23
  4931.2 1956.51    4942 1953.97  4949.2 1951.48  4953.4 1950.76  4960.1  1948.3
    4965 1947.19  4974.5 1943.26  4986.6 1935.15  4999.9 1928.09  5000.2 1927.39
  5000.5 1926.89    5004 1926.89  5004.2 1927.39  5010.7 1933.35    5015  1936.2
  5037.9 1947.15  5044.7 1949.42  5053.1 1953.18  5062.5 1955.42  5070.6 1958.45
#Mann= 3 ,-1 , 0
  4819.6      .1       0  5000.2     .05       0  5004.2      .1       0
Bank Sta=5000.2,5004.2
XS Rating Curve= 0 ,0
Exp/Cntr=0.3,0.1

Type RM Length L Ch R = 1 ,42639   ,338,338,338
BEGIN DESCRIPTION:
Quinlan Creek 81.0
END DESCRIPTION:
XS GIS Cut Line= 3
      1946225.01     13945224.99        1946175.       13945325.
      1946024.98     13945575.03
#Sta/Elev= 30
  4888.2 1973.76  4902.4 1967.88  4923.8 1961.03  4947.1 1951.89  4953.8 1947.67
  4957.1  1944.4  4970.5 1934.23  4974.1 1932.38  4983.9 1925.13  4987.3 1921.59
  4995.3 1916.84  4995.6 1916.34  4999.1 1916.34  4999.3 1916.84  5007.8 1920.06
  5023.7 1922.42  5028.7 1924.31  5034.6 1927.63  5042.7 1930.62  5095.8 1939.03
    5098 1939.87  5113.3 1941.64  5133.7 1945.83  5137.2  1947.2  5178.5 1956.49
  5235.2 1970.64  5256.1 1978.74  5266.6 1981.91  5277.1 1983.64  5291.6 1984.68
#Mann= 4 ,-1 , 0
  4888.2      .1       0  4974.1     .07       0  4995.3     .05       0
  4999.3     .07       0
Bank Sta=4995.3,4999.3
XS Rating Curve= 0 ,0
Exp/Cntr=0.3,0.1

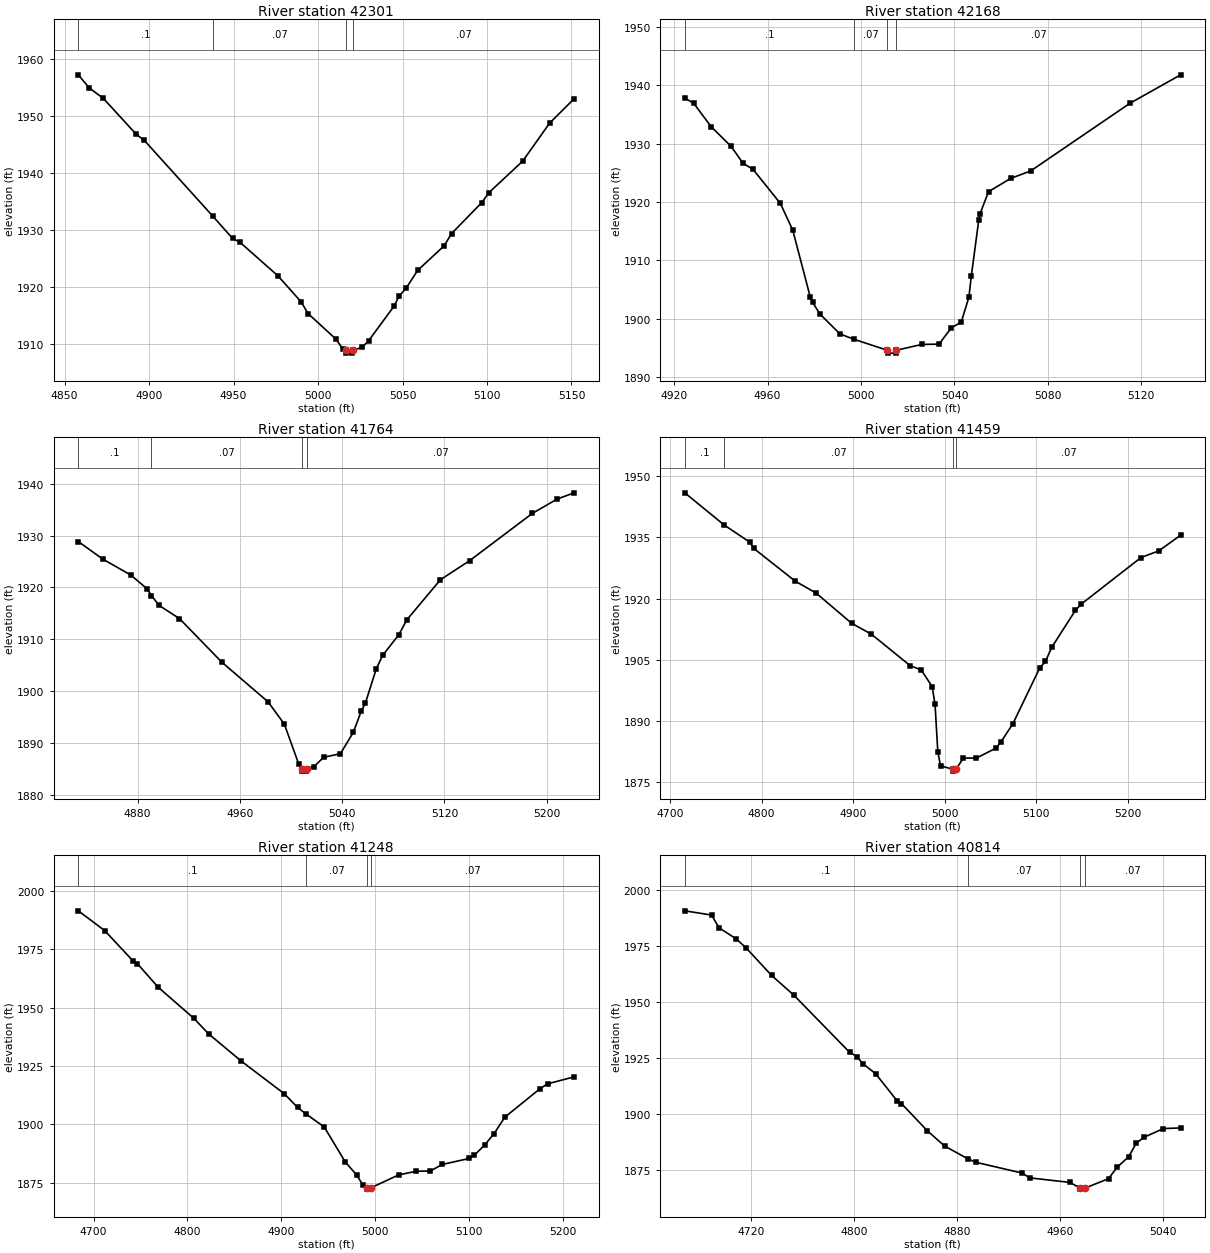
Type RM Length L Ch R = 1 ,42301   ,133,133,133
BEGIN DESCRIPTION:
Mapping XS 03d01310
END DESCRIPTION:
XS GIS Cut Line= 2
      1945982.38      13945082.7      1945785.37     13945300.26
#Sta/Elev= 30
  4858.1 1957.26  4864.5 1954.98  4872.9 1953.13  4892.3 1946.86  4897.1 1945.78
  4937.7 1932.48  4949.4 1928.58  4953.8  1927.9  4976.3 1922.01    4990 1917.45
  4994.1  1915.4  5010.5 1910.95  5014.5 1909.27  5016.6 1908.97  5016.8 1908.47
  5020.3 1908.47  5020.6 1908.97  5026.1 1909.49  5029.9 1910.63  5045.2 1916.79
  5047.8 1918.42  5052.2 1919.88    5059 1922.99  5074.6 1927.27    5079 1929.42
  5096.9 1934.86  5101.2 1936.62  5121.1 1942.12  5137.1  1948.8  5151.6 1953.07
#Mann= 4 ,-1 , 0
  4858.1      .1       0  4937.7     .07       0  5016.6     .05       0
  5020.6     .07       0
Bank Sta=5016.6,5020.6
XS Rating Curve= 0 ,0
Exp/Cntr=0.3,0.1

Type RM Length L Ch R = 1 ,42168   ,404,404,404
BEGIN DESCRIPTION:
Quinlan Creek 80.0
END DESCRIPTION:
XS GIS Cut Line= 3
      1945875.03     13945024.97        1945825.       13945075.
      1945724.98     13945175.02
#Sta/Elev= 30
  4924.6  1937.8  4928.4 1936.92  4935.9 1932.89  4944.3 1929.58  4949.6  1926.6
  4953.8 1925.59  4965.5 1919.75  4970.8 1915.17  4978.3 1903.69  4979.3 1902.78
  4982.5 1900.76    4991 1897.38  4997.1 1896.45  5011.2 1894.59  5011.5 1894.09
    5015 1894.09  5015.2 1894.59    5026 1895.58  5033.4 1895.63  5038.7 1898.44
  5042.9 1899.39  5046.2  1903.7  5047.2 1907.26  5050.4 1916.88  5050.9 1917.92
  5054.6 1921.77  5064.1 1924.04  5072.6 1925.31  5115.1 1936.91  5136.8 1941.79
#Mann= 4 ,-1 , 0
  4924.6      .1       0  4997.1     .07       0  5011.2     .05       0
  5015.2     .07       0
Bank Sta=5011.2,5015.2
XS Rating Curve= 0 ,0
Exp/Cntr=0.3,0.1

Type RM Length L Ch R = 1 ,41764   ,305,305,305
BEGIN DESCRIPTION:
Quinlan Creek 79.0
END DESCRIPTION:
XS GIS Cut Line= 3
      1945675.03     13944774.99      1945517.17     13944827.12
      1945430.36     13945030.86
#Sta/Elev= 30
  4833.7 1928.88  4852.6 1925.51  4874.7 1922.41  4887.4 1919.76  4890.9 1918.43
  4896.8 1916.55  4912.8 1913.99  4945.8  1905.6  4982.1 1897.91  4994.8 1893.61
    5006 1885.92  5008.4 1885.04  5008.6 1884.54  5012.1 1884.54  5012.4 1885.04
  5018.1 1885.43  5025.5 1887.21  5038.6  1887.9  5048.7 1892.02  5054.9 1896.12
  5058.1 1897.65  5066.7 1904.31  5071.6 1906.87  5084.2 1910.85  5090.7  1913.8
  5116.8 1921.49  5139.7 1925.19  5188.6 1934.29  5208.1 1937.08  5221.4 1938.28
#Mann= 4 ,-1 , 0
  4833.7      .1       0  4890.9     .07       0  5008.4     .05       0
  5012.4     .07       0
Bank Sta=5008.4,5012.4
XS Rating Curve= 0 ,0
Exp/Cntr=0.3,0.1

Type RM Length L Ch R = 1 ,41459   ,211,211,211
BEGIN DESCRIPTION:
Quinlan Creek 78.1
END DESCRIPTION:
XS GIS Cut Line= 4
      1945764.67     13944749.53      1945603.97     13944625.62
      1945456.66      13944609.3      1945281.15     13944683.02
#Sta/Elev= 30
  4716.1 1945.91  4759.1 1938.02    4787 1933.83  4791.4 1932.29  4836.8 1924.24
  4859.5 1921.35  4898.2 1913.95  4919.8 1911.27  4962.2 1903.56  4974.3  1902.5
  4986.3 1898.41  4989.4 1894.07  4992.4 1882.48  4995.4 1878.99  5008.5  1878.2
  5008.7  1877.7  5012.5  1878.2  5020.3  1880.9  5034.6  1880.9  5055.7 1883.31
  5061.1 1884.76  5074.4 1889.31  5103.7 1902.98    5110 1904.58  5116.8 1908.02
  5142.7  1917.1  5149.2 1918.67  5214.3 1930.04  5233.8 1931.69  5257.6 1935.53
#Mann= 4 ,-1 , 0
  4716.1      .1       0  4759.1     .07       0  5008.5     .05       0
  5012.5     .07       0
Bank Sta=5008.5,5012.5
XS Rating Curve= 0 ,0
Exp/Cntr=0.3,0.1

Type RM Length L Ch R = 1 ,41248   ,434,434,434
BEGIN DESCRIPTION:
Quinlan Creek 78.0
END DESCRIPTION:
XS GIS Cut Line= 3
      1945574.99     13944125.03        1945475.       13944425.
      1945325.02     13944574.98
#Sta/Elev= 30
  4683.8 1991.41  4711.9 1982.95  4741.9 1970.05  4746.6 1968.86  4768.8 1958.74
  4806.7 1945.49  4822.6 1938.77  4857.3 1927.14  4903.2 1913.16  4917.4 1907.29
  4926.9 1904.35  4945.8 1898.94    4968  1884.1  4980.7 1878.21    4987 1874.03
  4991.2 1872.84  4991.5 1872.34  4995.2 1872.84    5025 1878.41  5043.7 1879.98
  5058.9 1880.11  5071.6  1882.9  5100.1 1885.45  5105.6 1886.77  5117.1 1891.37
  5126.8 1896.12  5138.3 1903.14  5175.3 1915.17  5183.7 1917.38  5212.1 1920.37
#Mann= 4 ,-1 , 0
  4683.8      .1       0  4926.9     .07       0  4991.2     .05       0
  4995.2     .07       0
Bank Sta=4991.2,4995.2
XS Rating Curve= 0 ,0
Exp/Cntr=0.3,0.1

Type RM Length L Ch R = 1 ,40814   ,439,439,439
BEGIN DESCRIPTION:
Quinlan Creek 77.0
END DESCRIPTION:
XS GIS Cut Line= 3
      1945224.98     13944025.04        1945075.       13944325.
        1945075.     13944375.04
#Sta/Elev= 30
  4668.5 1990.81  4689.3 1988.93  4695.1 1983.23  4708.5 1978.26  4716.1 1974.29
    4736 1961.93    4753 1953.28  4796.6 1927.63  4802.5 1925.66  4806.7 1922.61
  4816.8 1918.08  4833.5 1905.96  4836.9 1904.73    4857 1892.58  4870.4 1885.77
  4888.3 1880.12  4894.7  1878.5  4930.8 1873.67  4936.6 1871.54  4967.7 1869.52
  4975.8 1867.01    4976 1866.51  4979.8 1867.01  4997.9 1871.18  5004.4  1876.2
  5013.5 1880.97  5019.5  1887.1  5025.5 1889.69  5040.5 1893.55  5053.9 1893.85
#Mann= 4 ,-1 , 0
  4668.5      .1       0  4888.3     .07       0  4975.8     .05       0
  4979.8     .07       0
Bank Sta=4975.8,4979.8
XS Rating Curve= 0 ,0
Exp/Cntr=0.3,0.1

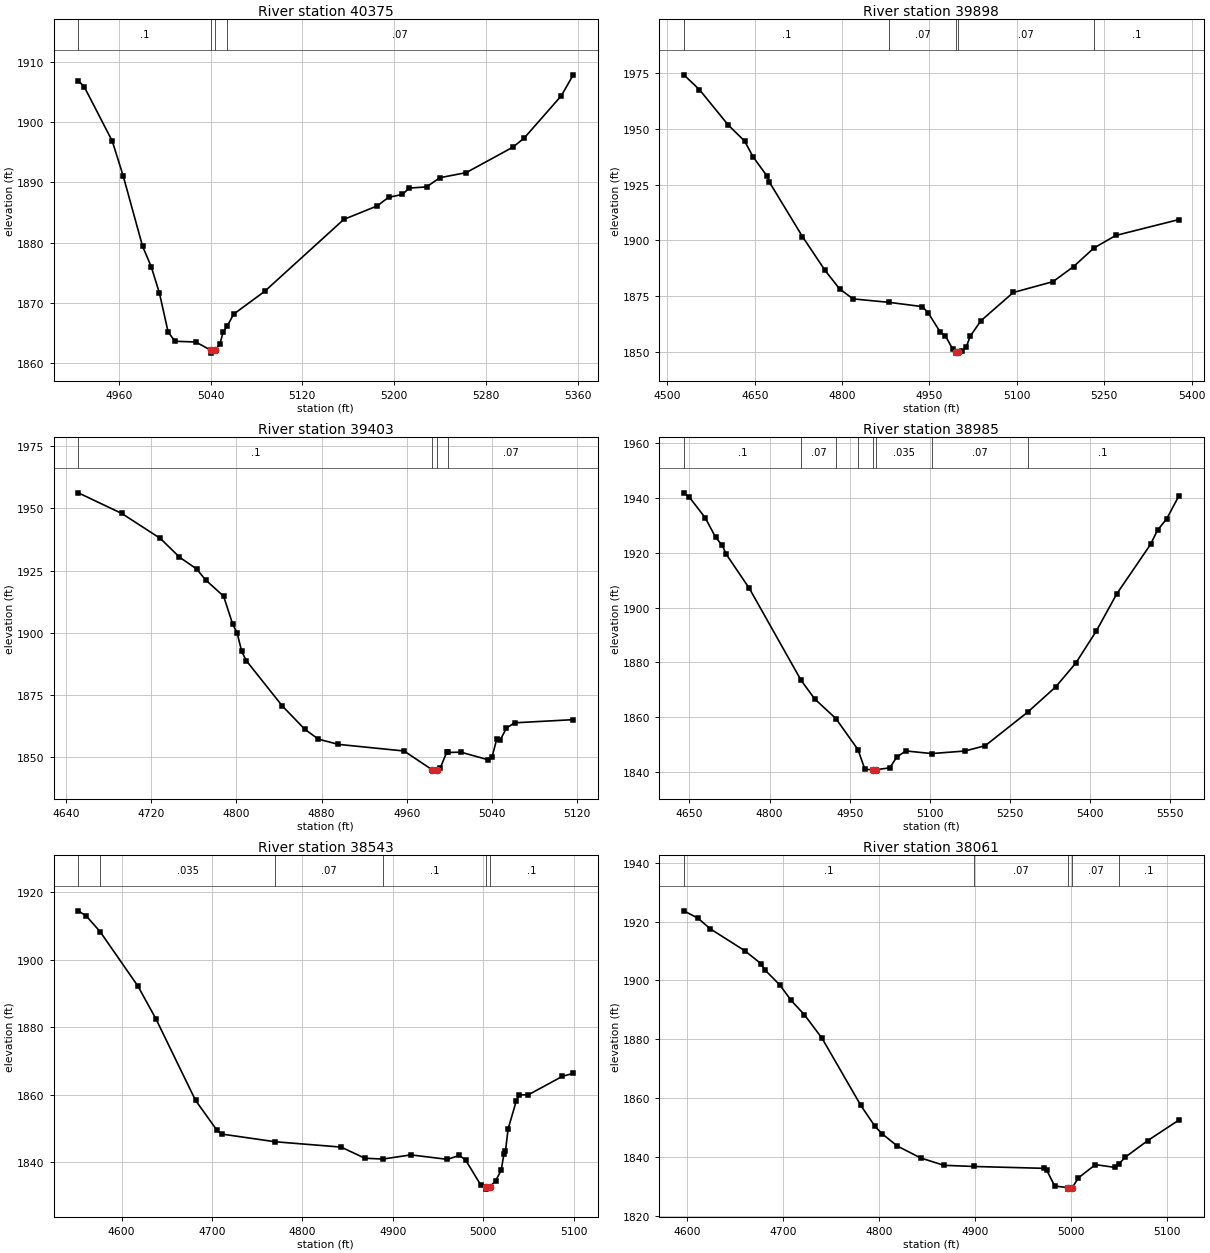
Type RM Length L Ch R = 1 ,40375   ,477,477,477
BEGIN DESCRIPTION:
Quinlan Creek 76.0
END DESCRIPTION:
XS GIS Cut Line= 4
      1944774.97     13944025.03        1944725.       13944075.
        1944725.       13944275.      1944712.41     13944435.04
#Sta/Elev= 30
  4924.8 1906.87  4929.9  1905.9  4954.4 1896.85  4963.9 1891.08  4980.8 1879.38
  4988.3 1876.02  4995.5 1871.59  5003.1 1865.11  5009.1  1863.6  5027.1 1863.48
  5040.1 1862.13  5040.4 1861.63  5044.1 1862.13  5048.1 1863.13  5051.1 1865.19
  5054.5 1866.09  5060.1  1868.1  5087.1 1871.88  5156.1 1883.84  5185.2 1886.08
  5195.1 1887.51  5207.1 1887.99  5213.2 1889.05  5228.2 1889.24  5239.8 1890.77
  5262.7 1891.61  5303.4 1895.84  5313.2 1897.34  5345.6 1904.38    5356 1907.86
#Mann= 4 ,-1 , 0
  4924.8      .1       0  5040.1     .05       0  5044.1      .1       0
  5054.5     .07       0
Bank Sta=5040.1,5044.1
XS Rating Curve= 0 ,0
Exp/Cntr=0.3,0.1

Type RM Length L Ch R = 1 ,39898   ,495,495,495
BEGIN DESCRIPTION:
Quinlan Creek 75.0
END DESCRIPTION:
XS GIS Cut Line= 4
        1944575.       13943475.        1944325.       13943875.
        1944225.       13943925.      1943996.24     13944060.93
#Sta/Elev= 30
  4528.3 1974.22    4555 1967.63  4604.5 1951.74  4632.8 1944.49    4647 1937.54
  4671.6 1928.67  4675.3 1926.08  4731.9 1901.74  4770.8 1886.53  4795.6  1878.3
  4818.7 1873.78  4881.1 1872.22  4937.6 1870.32  4947.7 1867.56  4968.9 1858.72
  4977.2 1857.36  4990.1 1851.13  4995.2 1849.97  4995.5 1849.47  4999.2 1849.97
  5006.6 1850.34  5013.3 1852.29    5020  1857.1  5038.4    1864  5093.8 1876.65
    5162 1881.51  5197.3 1888.25  5232.2 1896.58  5269.8 1902.22  5377.9 1909.32
#Mann= 5 ,-1 , 0
  4528.3      .1       0  4881.1     .07       0  4995.2     .05       0
  4999.2     .07       0  5232.2      .1       0
Bank Sta=4995.2,4999.2
XS Rating Curve= 0 ,0
Exp/Cntr=0.3,0.1

Type RM Length L Ch R = 1 ,39403   ,418,418,418
BEGIN DESCRIPTION:
Quinlan Creek 74.0
END DESCRIPTION:
XS GIS Cut Line= 3
      1944224.97     13943275.03        1943975.       13943525.
      1943925.01     13943624.99
#Sta/Elev= 30
  4651.3  1956.3  4692.2    1948  4728.5 1937.94  4746.4 1930.44  4762.5 1925.69
    4771 1921.26  4787.9 1914.74  4796.4 1903.54  4800.7 1899.81  4804.9 1892.56
  4809.2 1888.81  4843.1 1870.57  4864.3 1861.18    4877 1857.24  4895.8 1855.13
  4957.6 1852.46  4984.1 1844.87  4984.4 1844.37  4988.1 1844.87  4991.6 1845.66
  4997.6 1851.88  4998.5 1851.88  5011.1 1851.99  5036.5 1848.94  5040.4 1850.25
  5044.7 1857.29    5048 1856.94  5053.8 1861.69  5061.4  1863.8  5116.6 1865.07
#Mann= 4 ,-1 , 0
  4651.3      .1       0  4984.1     .05       0  4988.1      .1       0
  4998.5     .07       0
Bank Sta=4984.1,4988.1
XS Rating Curve= 0 ,0
Exp/Cntr=0.3,0.1

Type RM Length L Ch R = 1 ,38985   ,442,442,442
BEGIN DESCRIPTION:
Quinlan Creek 73.0
END DESCRIPTION:
XS GIS Cut Line= 3
      1944024.98     13943025.02        1943725.       13943225.
      1943325.01     13943624.99
#Sta/Elev= 30
  4639.5 1941.93  4649.3 1940.49  4679.6 1932.82    4699  1925.7  4711.5 1922.75
  4718.7 1919.57    4762 1907.08  4859.1 1873.46  4884.6 1866.67  4924.1 1859.54
  4965.4  1848.2  4978.3 1841.02  4994.2 1840.85  4994.5 1840.35  4998.5 1840.85
    5025 1841.55  5038.1 1845.52  5055.1 1847.71  5103.5 1846.76  5165.4 1847.69
  5203.6 1849.64  5282.9 1861.87  5335.1 1871.03  5372.9 1879.75  5411.1 1891.38
  5449.4 1904.96  5512.9 1923.11    5526 1928.32    5543  1932.4  5565.7 1940.72
#Mann= 8 ,-1 , 0
  4639.5      .1       0  4859.1     .07       0  4924.1      .1       0
  4965.4    .035       0  4994.2    .035       0  4998.5    .035       0
  5103.5     .07       0  5282.9      .1       0
Bank Sta=4994.2,4998.5
XS Rating Curve= 0 ,0
Exp/Cntr=0.3,0.1

Type RM Length L Ch R = 1 ,38543   ,482,482,482
BEGIN DESCRIPTION:
Quinlan Creek 72.0
END DESCRIPTION:
XS GIS Cut Line= 3
      1943775.02     13942824.99        1943375.       13943025.
      1943275.04       13943025.
#Sta/Elev= 30
  4552.2 1914.45  4561.1  1912.9  4576.2 1908.32  4618.1 1892.16  4638.2 1882.36
  4681.8 1858.32  4705.3 1849.54  4710.7 1848.33  4769.9 1846.05  4842.8 1844.47
    4869 1841.17  4888.9 1840.93    4920 1842.16  4960.2 1840.84  4973.6    1842
  4980.4 1840.64  4997.1 1833.27  5002.6 1832.52  5002.9 1832.02  5006.9 1832.52
  5013.7 1834.55  5019.7 1837.62  5022.7  1842.3  5024.4 1843.17  5027.4 1849.87
  5036.4  1858.1  5039.4 1859.92  5049.7 1859.95  5087.4 1865.43  5099.4  1866.3
#Mann= 6 ,-1 , 0
  4552.2      .1       0  4576.2    .035       0  4769.9     .07       0
  4888.9      .1       0  5002.6     .05       0  5006.9      .1       0
Bank Sta=5002.6,5006.9
XS Rating Curve= 0 ,0
Exp/Cntr=0.3,0.1

Type RM Length L Ch R = 1 ,38061   ,467,467,467
BEGIN DESCRIPTION:
Quinlan Creek 71.0
END DESCRIPTION:
XS GIS Cut Line= 3
      1943825.03     13942775.02        1943475.       13942575.
      1943375.04     13942624.98
#Sta/Elev= 30
  4596.9 1923.64  4611.8 1921.11  4624.3 1917.55  4660.2 1910.13    4677 1905.75
  4680.9 1903.71  4696.8 1898.47  4708.6 1893.21  4722.4 1888.35  4740.8 1880.33
  4781.1 1857.56  4795.8 1850.47  4803.2 1847.95  4819.1 1843.78  4843.3 1839.75
  4867.5 1837.25  4898.6 1836.86  4971.7 1836.23  4974.6  1835.5  4982.7 1830.23
  4996.7 1829.67  4996.9 1829.17    5001 1829.67  5007.4 1832.99  5025.1 1837.49
  5045.8 1836.52  5049.5  1837.7  5055.9 1839.95  5079.3  1845.6  5111.8 1852.58
#Mann= 5 ,-1 , 0
  4596.9      .1       0  4898.6     .07       0  4996.7     .05       0
    5001     .07       0  5049.5      .1       0
Bank Sta=4996.7,5001
XS Rating Curve= 0 ,0
Exp/Cntr=0.3,0.1

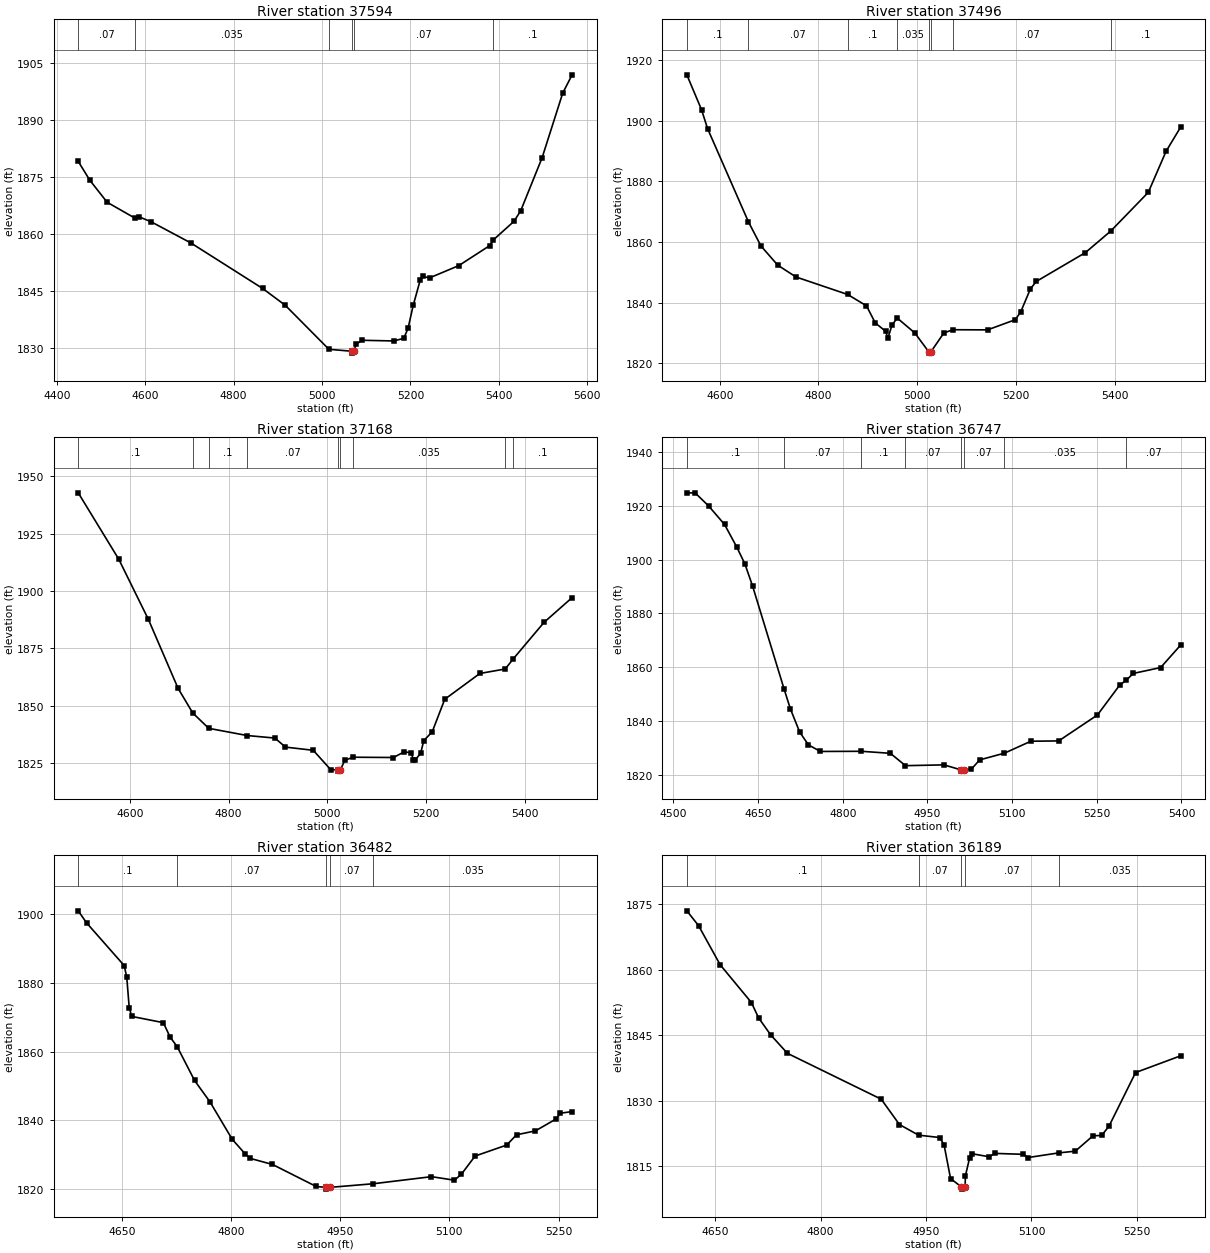
Type RM Length L Ch R = 1 ,37594   ,98,98,98
BEGIN DESCRIPTION:
Quinlan Creek 70.0
END DESCRIPTION:
XS GIS Cut Line= 3
       1943925.3      13942140.8        1943375.       13942175.
       1942975.1      13942574.9
#Sta/Elev= 30
  4448.7 1879.12    4475 1874.15  4514.1 1868.37    4576 1864.26  4586.2 1864.54
  4613.2 1863.26  4703.4 1857.67  4865.7  1845.7  4916.8 1841.28  5015.6  1829.7
    5067 1829.19  5067.3 1828.69  5071.6 1829.19  5077.7 1831.06  5090.5 1832.07
  5162.6 1831.89    5185  1832.6  5194.7 1835.27  5206.2 1841.24    5222 1847.86
  5227.4 1848.89  5243.2 1848.48  5309.3 1851.71    5379 1856.95  5387.8 1858.51
  5434.1 1863.35  5449.3 1866.12  5497.8  1880.1  5544.4  1897.1  5565.6 1901.89
#Mann= 6 ,-1 , 0
  4448.7     .07       0    4576    .035       0  5015.6     .07       0
    5067    .035       0  5071.6     .07       0  5387.8      .1       0
Bank Sta=5067,5071.6
XS Rating Curve= 0 ,0
Exp/Cntr=0.3,0.1

Type RM Length L Ch R = 1 ,37496   ,328,328,328
BEGIN DESCRIPTION:
Mapping XS 475c3f74
END DESCRIPTION:
XS GIS Cut Line= 3
      1943407.74     13941671.74      1943295.38     13942137.05
      1942952.71     13942530.19
#Sta/Elev= 30
  4533.4 1915.22  4563.1 1903.71  4575.5 1897.41  4658.2 1866.63  4683.5 1858.69
  4717.4 1852.36  4754.5 1848.44    4859 1842.67  4897.2 1838.92    4915 1833.27
  4935.8 1830.53  4940.7 1828.25  4948.9 1832.58  4959.5 1834.87  4995.2 1829.94
    5023 1823.79  5023.3 1823.29    5028 1823.79    5054 1829.98  5072.5 1831.02
  5142.4 1830.97  5198.2 1834.31  5209.2 1836.77  5229.1 1844.48    5241 1846.96
  5340.5 1856.49  5391.8  1863.6  5467.9 1876.39  5503.9 1889.95  5533.6 1897.99
#Mann= 8 ,-1 , 0
  4533.4      .1       0  4658.2     .07       0    4859      .1       0
  4959.5    .035       0    5023    .035       0    5028    .035       0
  5072.5     .07       0  5391.8      .1       0
Bank Sta=5023,5028
XS Rating Curve= 0 ,0
Exp/Cntr=0.3,0.1

Type RM Length L Ch R = 1 ,37168   ,421,421,421
BEGIN DESCRIPTION:
Quinlan Creek 69.0
END DESCRIPTION:
XS GIS Cut Line= 3
        1943325.       13941575.        1943025.       13941975.
        1942725.       13942375.
#Sta/Elev= 30
  4495.5 1942.74  4577.6 1913.83  4637.6 1887.63  4697.6 1857.68  4727.4 1846.93
  4759.7 1840.26  4837.5 1837.12  4893.7 1836.02  4915.1 1832.08  4971.3  1830.7
  5006.6  1822.3  5021.2 1822.13  5021.6 1821.63  5026.2 1822.13  5035.1 1826.29
  5051.5 1827.68  5133.7 1827.56  5155.1 1829.96  5170.1 1829.68  5173.7 1826.51
  5178.1 1826.57  5188.7 1829.37  5195.2 1834.91  5212.3 1838.77  5237.6  1852.9
  5308.7 1864.13  5360.1 1866.08  5376.4  1870.5  5438.7 1886.38  5495.5 1897.14
#Mann= 9 ,-1 , 0
  4495.5      .1       0  4727.4     .07       0  4759.7      .1       0
  4837.5     .07       0  5021.2     .05       0  5026.2     .07       0
  5051.5    .035       0  5360.1     .07       0  5376.4      .1       0
Bank Sta=5021.2,5026.2
XS Rating Curve= 0 ,0
Exp/Cntr=0.3,0.1

Type RM Length L Ch R = 1 ,36747   ,265,265,265
BEGIN DESCRIPTION:
Quinlan Creek 68.0
END DESCRIPTION:
XS GIS Cut Line= 3
      1942925.01     13941424.98        1942675.       13941825.
        1942625.     13942224.97
#Sta/Elev= 30
  4523.9 1924.86  4538.8  1924.8  4562.4 1919.99  4590.7 1913.08    4612 1904.81
  4626.7 1898.42  4640.3  1890.2  4695.9 1852.02  4707.2 1844.51  4723.8 1835.81
  4739.3 1831.05  4760.5 1828.61  4833.1 1828.67  4884.4 1827.92  4911.2 1823.32
  4979.4 1823.62  5008.9 1821.79  5009.3 1821.29    5014 1821.79  5027.5 1821.94
  5042.6 1825.47  5086.5 1827.98  5133.3 1832.42  5182.5 1832.53  5251.2 1842.19
  5290.5 1853.28  5301.7 1855.03  5314.7 1857.65  5363.1 1859.83  5398.7 1868.23
#Mann= 8 ,-1 , 0
  4523.9      .1       0  4695.9     .07       0  4833.1      .1       0
  4911.2     .07       0  5008.9     .05       0    5014     .07       0
  5086.5    .035       0  5301.7     .07       0
Bank Sta=5008.9,5014
XS Rating Curve= 0 ,0
Exp/Cntr=0.3,0.1

Type RM Length L Ch R = 1 ,36482   ,293,293,293
BEGIN DESCRIPTION:
Quinlan Creek 67.0
END DESCRIPTION:
XS GIS Cut Line= 3
      1942774.98     13941425.01      1942501.52       13941581.
      1942385.41     13941926.07
#Sta/Elev= 30
  4589.8  1900.9  4601.2 1897.42    4653 1884.98  4656.5 1881.63  4659.9 1872.71
  4663.4 1870.22  4706.8  1868.4  4716.2 1864.17  4725.8 1861.43  4749.7  1851.6
  4770.7 1845.45  4801.5  1834.5  4818.9 1830.36  4826.4 1828.95  4856.8  1827.2
  4916.9  1820.8  4930.2 1820.53  4930.6 1820.03  4935.3 1820.53  4995.6  1821.6
  5075.4 1823.65  5106.8 1822.63  5116.3  1824.3  5135.3 1829.64  5178.8 1832.84
  5192.3 1835.82  5218.2 1836.95  5246.1 1840.35  5252.4 1842.09  5268.7 1842.56
#Mann= 5 ,-1 , 0
  4589.8      .1       0  4725.8     .07       0  4930.2    .035       0
  4935.3     .07       0  4995.6    .035       0
Bank Sta=4930.2,4935.3
XS Rating Curve= 0 ,0
Exp/Cntr=0.3,0.1

Type RM Length L Ch R = 1 ,36189   ,319,319,319
BEGIN DESCRIPTION:
Mapping XS edc2efed
END DESCRIPTION:
XS GIS Cut Line= 3
      1942389.18     13941221.08      1942249.21     13941477.06
      1942195.22     13941884.25
#Sta/Elev= 30
  4609.8 1873.53  4626.4 1870.15  4657.2 1861.18  4701.6 1852.54  4711.9 1849.01
    4729 1845.14  4752.9  1840.9  4886.3  1830.4  4912.2  1824.6  4939.4 1822.17
  4969.7 1821.62  4975.8 1819.85  4984.9 1812.23  5000.4 1810.31  5000.8 1809.81
  5005.6 1810.31    5006 1812.84  5012.1 1817.01  5015.3 1817.92  5039.3 1817.23
  5048.4 1817.99  5087.8 1817.78  5095.5 1817.05  5138.5  1818.1  5162.3  1818.5
  5187.6 1822.03  5199.8 1822.09  5210.3 1824.23  5248.1  1836.5  5312.3 1840.34
#Mann= 5 ,-1 , 0
  4609.8      .1       0  4939.4     .07       0  5000.4     .05       0
  5005.6     .07       0  5138.5    .035       0
Bank Sta=5000.4,5005.6
XS Rating Curve= 0 ,0
Exp/Cntr=0.3,0.1

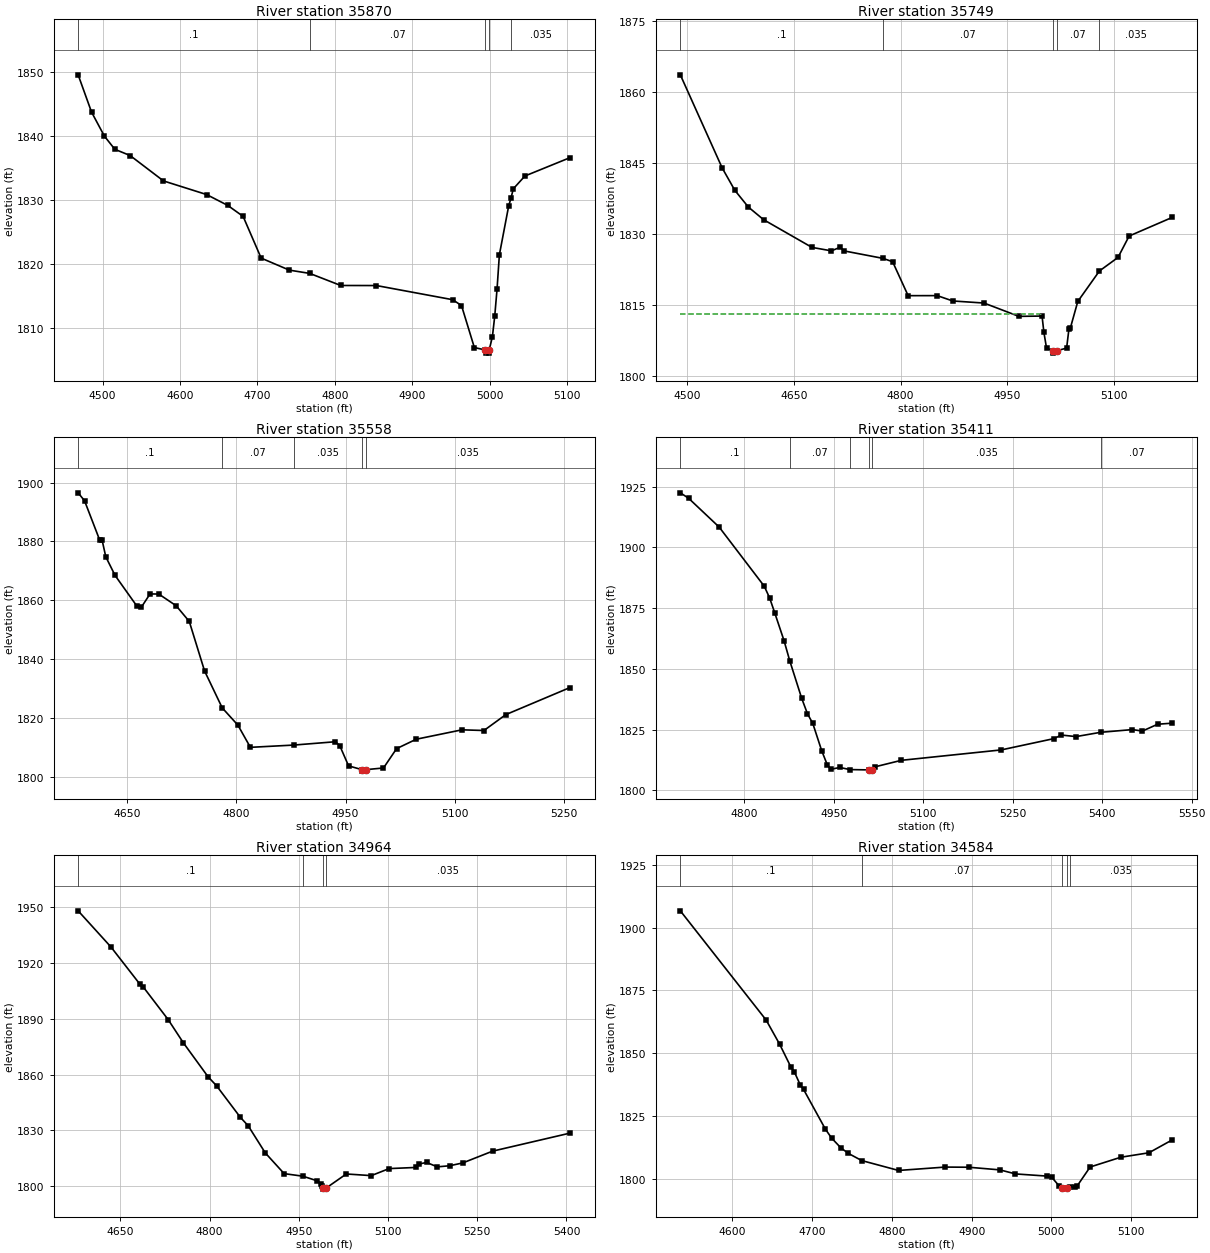
Type RM Length L Ch R = 1 ,35870   ,121,121,121
BEGIN DESCRIPTION:
Quinlan Creek 66.0
END DESCRIPTION:
XS GIS Cut Line= 3
      1942203.54     13941241.01        1941975.       13941725.
        1941975.     13941824.96
#Sta/Elev= 30
  4468.5 1849.61  4485.8 1843.79  4502.4 1840.03  4515.9 1837.97  4535.6    1837
  4578.7 1833.03  4634.4  1830.9  4661.6 1829.21  4681.5 1827.49  4704.8 1820.97
  4741.2 1819.09  4767.5 1818.58  4807.6 1816.69  4853.7 1816.68    4952 1814.47
  4963.5 1813.56  4980.1 1806.99  4994.1 1806.62  4994.5 1806.12  4998.9 1806.12
  4999.3 1806.62  5003.4 1808.69  5006.4 1811.88  5009.4 1816.12  5012.4 1821.48
  5024.4 1829.11  5027.4 1830.35  5030.4  1831.8  5045.4  1833.8  5103.7 1836.67
#Mann= 5 ,-1 , 0
  4468.5      .1       0  4767.5     .07       0  4994.1     .05       0
  4999.3     .07       0  5027.4    .035       0
Bank Sta=4994.1,4999.3
XS Rating Curve= 0 ,0
Exp/Cntr=0.3,0.1

Type RM Length L Ch R = 1 ,35749   ,191,191,191
BEGIN DESCRIPTION:
Mapping XS 0a486aab
END DESCRIPTION:
XS GIS Cut Line= 3
      1941867.47     13941175.28      1941931.91     13941472.06
      1941819.15     13941842.58
#Sta/Elev= 30
  4490.7 1863.72  4549.5 1844.04  4567.2 1839.33  4586.2 1835.79  4607.7 1833.11
  4675.6 1827.26  4702.9 1826.53  4715.2 1827.29  4721.3  1826.5  4775.4 1824.94
  4788.9 1824.23  4810.7 1817.06  4851.5 1817.07  4873.4 1815.94  4917.3  1815.5
  4966.2 1812.69  4998.8 1812.75  5001.4 1809.29  5005.1 1805.98  5014.1 1805.42
  5014.5 1804.92  5019.3 1805.42  5033.3 1805.98  5036.5 1809.95  5038.4 1810.14
    5049 1815.84  5079.4 1822.28  5105.5 1825.14  5121.1 1829.66  5181.7  1833.6
#Mann= 5 ,-1 , 0
  4490.7      .1       0  4775.4     .07       0  5014.1     .05       0
  5019.3     .07       0  5079.4    .035       0
#XS Ineff= 2 , 0
            4997 1813.13
Permanent Ineff=
       F       F
Bank Sta=5014.1,5019.3
XS Rating Curve= 0 ,0
Exp/Cntr=0.3,0.1

Type RM Length L Ch R = 1 ,35558   ,147,147,147
BEGIN DESCRIPTION:
Quinlan Creek 65.0
END DESCRIPTION:
XS GIS Cut Line= 3
      1941710.65     13941148.89      1941715.62     13941451.69
        1941725.     13941825.03
#Sta/Elev= 30
  4582.3  1896.5  4591.1 1893.81  4612.1 1880.36  4615.1 1880.62  4620.3 1874.81
  4633.1 1868.47    4663  1858.1  4669.1 1857.66  4681.1 1862.19  4693.1 1862.18
  4717.1 1858.19  4735.1 1852.87  4756.1 1836.08  4780.4 1823.55  4801.9 1817.71
  4819.1 1810.17  4878.8 1810.94  4936.1 1812.07  4942.1 1810.66  4954.1 1803.88
  4972.5  1802.6  4972.9  1802.1  4977.7  1802.6  5002.1 1803.17  5020.1 1809.73
  5047.1 1812.92    5110 1816.11  5140.2 1815.88  5170.2 1821.26  5258.6 1830.46
#Mann= 5 ,-1 , 0
  4582.3      .1       0  4780.4     .07       0  4878.8    .035       0
  4972.5    .035       0  4977.7    .035       0
Bank Sta=4972.5,4977.7
XS Rating Curve= 0 ,0
Exp/Cntr=0.3,0.1

Type RM Length L Ch R = 1 ,35411   ,447,447,447
BEGIN DESCRIPTION:
Quinlan Creek 64.5
END DESCRIPTION:
XS GIS Cut Line= 4
       1941602.8     13941161.88      1941631.44     13941428.76
      1941592.37     13941501.68      1941510.35     13941967.78
#Sta/Elev= 30
  4693.1  1922.5  4706.8  1920.3  4758.2 1908.39  4833.7 1884.06  4842.7 1879.26
  4851.2 1873.16  4866.9 1861.63  4876.4 1853.41  4896.5 1837.88  4906.1 1831.57
  4915.1 1827.54    4930 1816.32  4939.3 1810.56  4945.3 1808.65  4960.4 1809.43
  4977.1 1808.55  5009.9 1808.41  5010.3 1807.91  5015.1 1808.41  5019.5 1809.69
  5063.5 1812.36    5231 1816.65  5319.4 1821.31  5331.6 1822.77  5356.2 1822.13
  5397.3 1823.89  5450.4 1825.01  5467.5 1824.41    5493 1827.22  5517.5 1827.66
#Mann= 6 ,-1 , 0
  4693.1      .1       0  4876.4     .07       0  4977.1    .035       0
  5009.9    .035       0  5015.1    .035       0  5397.3     .07       0
Bank Sta=5009.9,5015.1
XS Rating Curve= 0 ,0
Exp/Cntr=0.3,0.1

Type RM Length L Ch R = 1 ,34964   ,380,380,380
BEGIN DESCRIPTION:
Quinlan Creek 64.0
END DESCRIPTION:
XS GIS Cut Line= 3
        1941375.     13941174.99        1941225.       13941575.
        1941225.     13941974.99
#Sta/Elev= 30
  4578.9 1948.03  4634.1 1928.58  4682.1 1908.85  4688.1  1907.2  4730.2 1889.57
  4755.8 1877.06  4797.5 1858.74  4811.6 1853.97  4851.9 1836.89  4864.8 1832.46
  4893.6 1817.84  4925.3  1806.7  4956.7 1805.33  4980.1 1802.92  4986.5 1801.26
  4989.7 1799.97  4990.2 1798.87  4990.6 1798.37  4995.6 1798.87  5029.8 1806.52
  5071.8 1805.63  5101.8 1809.41  5146.8 1810.03  5152.8 1811.91  5164.8 1812.72
  5182.8 1810.35  5203.8 1810.94  5225.8 1812.48  5275.8 1818.79  5406.1  1828.5
#Mann= 4 ,-1 , 0
  4578.9      .1       0  4956.7    .035       0  4990.2    .035       0
  4995.6    .035       0
Bank Sta=4990.2,4995.6
XS Rating Curve= 0 ,0
Exp/Cntr=0.3,0.1

Type RM Length L Ch R = 1 ,34584   ,488,488,488
BEGIN DESCRIPTION:
Quinlan Creek 63.0
END DESCRIPTION:
XS GIS Cut Line= 3
      1941174.99     13941225.02      1940880.53      13941577.7
      1940824.99     13941725.03
#Sta/Elev= 30
  4534.7  1906.7  4642.3 1863.18  4659.3 1853.51  4673.6 1844.29  4677.5 1842.64
  4685.3 1837.18  4689.2 1835.55  4716.6 1819.71  4724.4 1816.15  4735.8 1812.32
  4745.2 1810.07  4762.2 1807.18  4808.4 1803.24  4866.9 1804.59  4896.4 1804.52
  4935.5 1803.47    4955 1801.86    4995 1800.98  5000.5 1800.51  5010.1 1796.93
  5013.7  1796.3  5014.2  1795.8  5019.3  1796.3  5023.1 1796.68  5029.4  1796.5
  5032.6 1797.19  5048.6 1804.62  5087.1 1808.51  5122.3 1810.28  5151.6 1815.43
#Mann= 5 ,-1 , 0
  4534.7      .1       0  4762.2     .07       0  5013.7     .05       0
  5019.3     .07       0  5023.1    .035       0
Bank Sta=5013.7,5019.3
XS Rating Curve= 0 ,0
Exp/Cntr=0.3,0.1