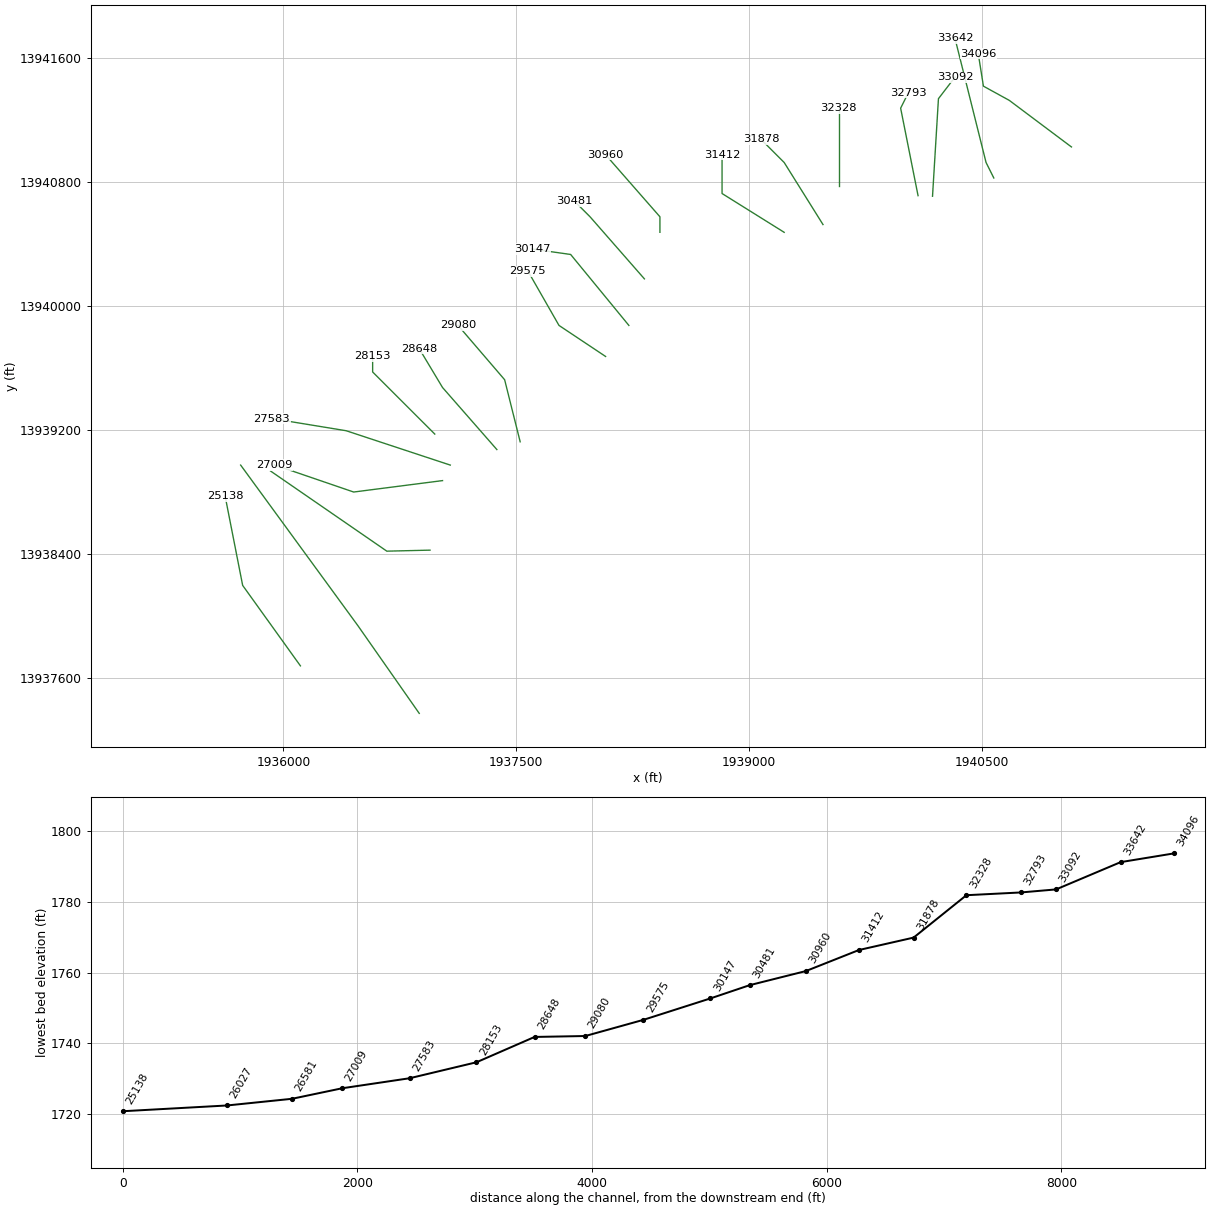
HEC-RAS study Quinlan Creek.prj: Quinlan Creek Base Level Engineering

--- Quinlan Creek.g01 (geometry) --- (continued)

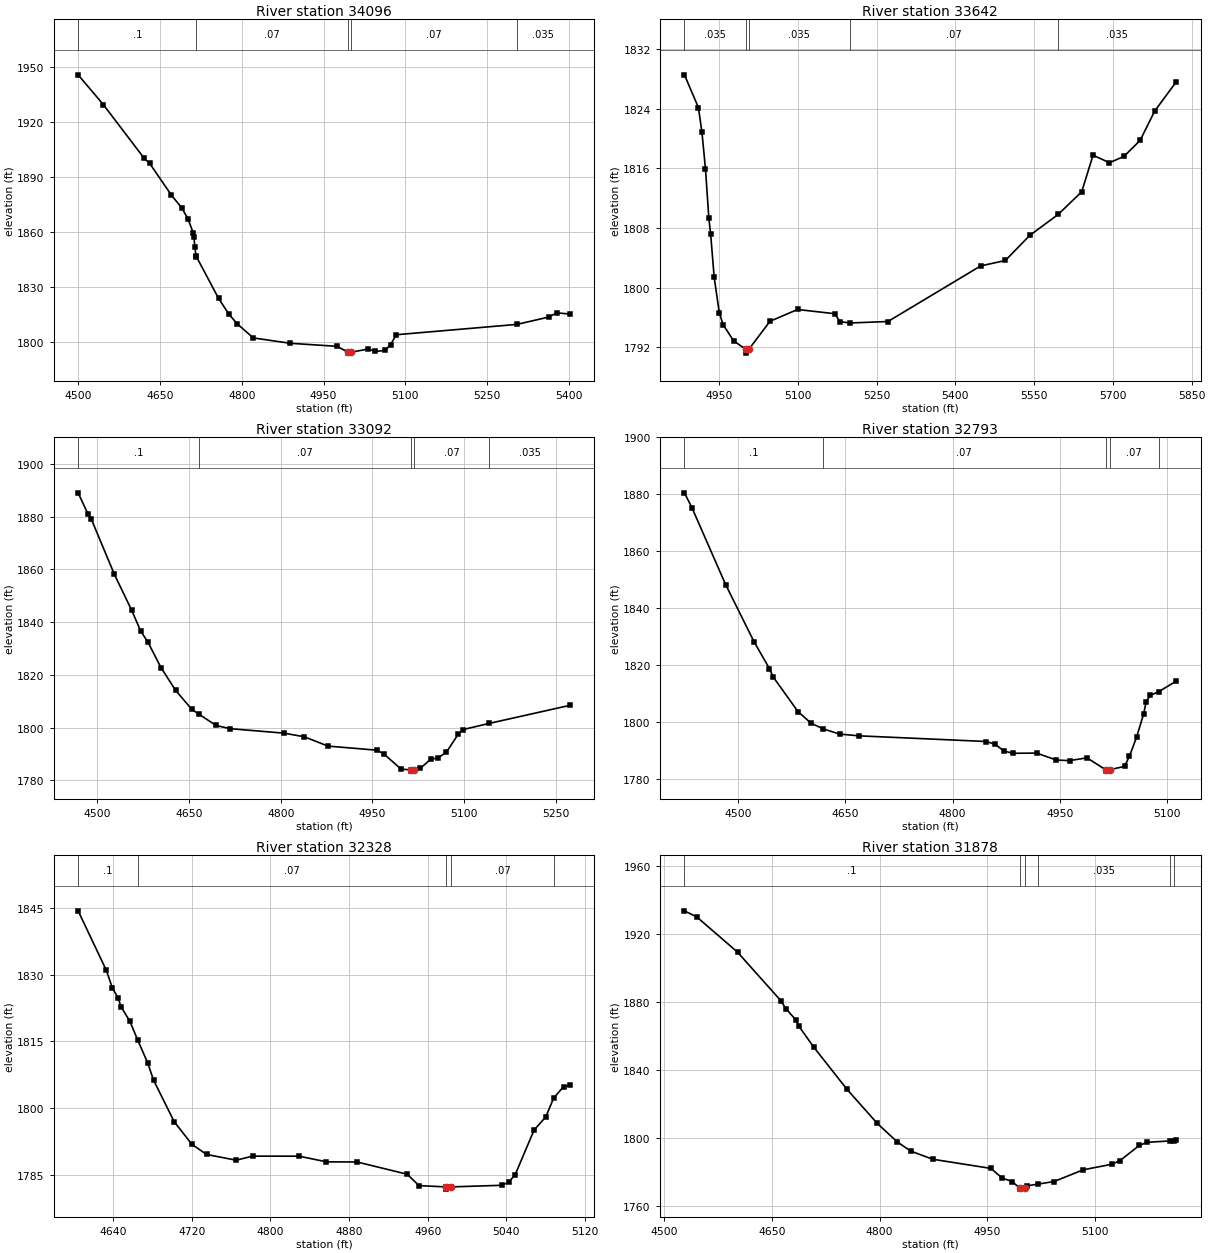
Type RM Length L Ch R = 1 ,34096   ,454,454,454
BEGIN DESCRIPTION:
Quinlan Creek 62.0
END DESCRIPTION:
XS GIS Cut Line= 4
      1941075.02     13941024.99        1940675.       13941325.
      1940508.12     13941416.83        1940475.     13941625.01
#Sta/Elev= 30
  4500.1 1945.61  4546.2 1929.41  4621.2 1900.04  4631.2  1897.3  4671.2  1879.9
    4690 1873.04  4701.2 1867.15  4711.2 1859.37  4712.5 1857.05  4714.1 1851.63
  4716.2 1846.85  4717.1 1846.27  4757.5 1823.62  4776.2  1815.1  4791.2 1809.85
  4821.2    1802  4888.8 1799.08    4975 1797.41  4994.7  1794.2  4995.2  1793.7
  5000.4  1794.2    5032 1795.94    5045  1794.6  5062.8 1795.19  5073.1 1798.38
  5083.4 1803.74  5304.4 1809.38  5362.6 1813.37  5377.7 1815.68  5401.4 1815.05
#Mann= 5 ,-1 , 0
  4500.1      .1       0  4717.1     .07       0  4994.7     .05       0
  5000.4     .07       0  5304.4    .035       0
Bank Sta=4994.7,5000.4
XS Rating Curve= 0 ,0
Exp/Cntr=0.3,0.1

Type RM Length L Ch R = 1 ,33642   ,550,550,550
BEGIN DESCRIPTION:
Quinlan Creek 61.0
END DESCRIPTION:
XS GIS Cut Line= 3
      1940574.99     13940825.02        1940525.       13940925.
        1940325.       13941725.
#Sta/Elev= 30
  4883.9 1828.54  4910.6 1824.14  4917.3 1820.82    4924 1815.92  4930.4 1809.33
  4933.8 1807.24  4940.5 1801.43  4950.3 1796.64  4957.5 1795.06  4977.4  1792.9
  5000.7 1791.73  5001.2 1791.23  5006.5 1791.73  5046.9  1795.5  5099.4 1797.08
  5170.6 1796.51  5179.8 1795.46  5198.9 1795.27  5271.6 1795.47  5448.1 1802.92
  5495.2 1803.65  5541.6 1807.01  5595.7 1809.82  5640.6 1812.86  5662.2 1817.76
  5693.5 1816.76    5721  1817.6  5751.9 1819.75  5779.7 1823.69  5820.3 1827.56
#Mann= 5 ,-1 , 0
  4883.9    .035       0  5000.7    .035       0  5006.5    .035       0
  5198.9     .07       0  5595.7    .035       0
Bank Sta=5000.7,5006.5
XS Rating Curve= 0 ,0
Exp/Cntr=0.3,0.1

Type RM Length L Ch R = 1 ,33092   ,299,299,299
BEGIN DESCRIPTION:
Quinlan Creek 60.0
END DESCRIPTION:
XS GIS Cut Line= 3
      1940180.32      13940707.3      1940218.46     13941336.07
        1940325.       13941475.
#Sta/Elev= 30
  4468.3 1889.02  4484.4 1881.01  4489.7 1879.15  4527.6 1858.14  4555.8  1844.6
  4570.8 1836.61  4582.9 1832.29  4603.9  1822.8  4627.9 1814.15  4654.5 1806.93
  4666.8 1805.01  4694.1 1800.83  4716.8 1799.62  4805.3 1797.92  4838.7 1796.54
  4877.4 1793.01  4957.7 1791.45    4969 1790.01  4997.3 1784.26  5012.8 1784.02
  5013.2 1783.52  5018.6 1784.02  5028.5 1784.55  5045.5 1788.01  5057.7 1788.53
  5071.5 1790.74  5090.8 1797.56  5098.2 1799.25  5141.4 1801.61  5273.3 1808.44
#Mann= 5 ,-1 , 0
  4468.3      .1       0  4666.8     .07       0  5012.8     .05       0
  5018.6     .07       0  5141.4    .035       0
Bank Sta=5012.8,5018.6
XS Rating Curve= 0 ,0
Exp/Cntr=0.3,0.1

Type RM Length L Ch R = 1 ,32793   ,465,465,465
BEGIN DESCRIPTION:
Quinlan Creek 59.0
END DESCRIPTION:
XS GIS Cut Line= 3
       1940087.1     13940711.22        1939975.       13941275.
      1940024.99     13941374.98
#Sta/Elev= 30
  4425.5 1880.47  4436.1 1875.19    4483 1848.24  4522.8  1828.1  4544.2 1818.71
  4549.4 1815.78    4584 1803.61  4602.3 1799.51  4618.9 1797.55  4642.1 1795.68
  4669.6 1795.06  4847.2 1793.07  4859.3  1792.1  4871.5 1789.79  4883.7 1788.93
  4917.4    1789  4944.9 1786.56  4963.3 1786.35  4987.7 1787.33  5013.7 1783.16
  5014.2 1782.66  5019.6 1783.16  5040.2 1784.34  5046.9 1787.82  5056.9 1794.53
    5067  1802.9  5070.4 1807.12  5076.1 1809.26  5087.6 1810.56  5112.1 1814.23
#Mann= 5 ,-1 , 0
  4425.5      .1       0  4618.9     .07       0  5013.7     .05       0
  5019.6     .07       0  5087.6    .035       0
Bank Sta=5013.7,5019.6
XS Rating Curve= 0 ,0
Exp/Cntr=0.3,0.1

Type RM Length L Ch R = 1 ,32328   ,450,450,450
BEGIN DESCRIPTION:
Quinlan Creek 58.0
END DESCRIPTION:
XS GIS Cut Line= 3
        1939575.     13940774.96        1939575.       13941175.
        1939575.     13941274.96
#Sta/Elev= 30
  4604.4 1844.31  4633.1 1830.96  4639.1  1827.1  4645.1 1824.75  4648.1 1822.76
  4657.1 1819.51  4665.1 1815.27  4675.1 1810.22  4681.1 1806.34  4702.1 1797.01
  4720.1 1791.93  4735.1 1789.65  4765.1 1788.37    4782 1789.28  4829.2 1789.27
    4857    1788  4888.1 1787.97  4939.1 1785.22  4951.1 1782.67  4978.1 1782.38
  4978.6 1781.88    4984 1782.38  5035.1 1782.74  5042.2  1783.4    5049 1785.16
  5068.1 1795.12  5080.1 1798.11  5088.1 1802.34  5098.1 1804.86  5104.4 1805.19
#Mann= 5 ,-1 , 0
  4604.4      .1       0  4665.1     .07       0  4978.1     .05       0
    4984     .07       0  5088.1      .1       0
Bank Sta=4978.1,4984
XS Rating Curve= 0 ,0
Exp/Cntr=0.3,0.1

Type RM Length L Ch R = 1 ,31878   ,466,466,466
BEGIN DESCRIPTION:
Quinlan Creek 57.0
END DESCRIPTION:
XS GIS Cut Line= 3
      1939475.01     13940524.98        1939225.       13940925.
      1939075.04     13941074.96
#Sta/Elev= 30
  4528.5 1933.39  4545.8 1929.77  4602.4 1909.09  4662.5 1880.65  4669.6 1875.89
  4683.1  1869.5  4687.3 1865.83  4708.5 1853.23  4754.5 1828.59  4796.7  1808.5
  4824.6 1797.62    4843 1792.29  4873.6 1787.46  4954.8 1782.06  4970.3 1776.44
  4984.5 1774.33  4995.1 1770.39  4995.6 1769.89  5002.1 1770.39  5004.4 1771.77
  5019.9 1772.82  5042.5 1774.35  5083.2 1781.24  5123.2 1784.52  5134.1 1786.58
  5161.3 1795.59  5172.3 1797.41  5203.6 1798.19  5209.2  1798.4  5212.3 1798.55
#Mann= 6 ,-1 , 0
  4528.5      .1       0  4995.1     .05       0  5002.1      .1       0
  5019.9    .035       0  5203.6     .07       0  5209.2    .035       0
Bank Sta=4995.1,5002.1
XS Rating Curve= 0 ,0
Exp/Cntr=0.3,0.1

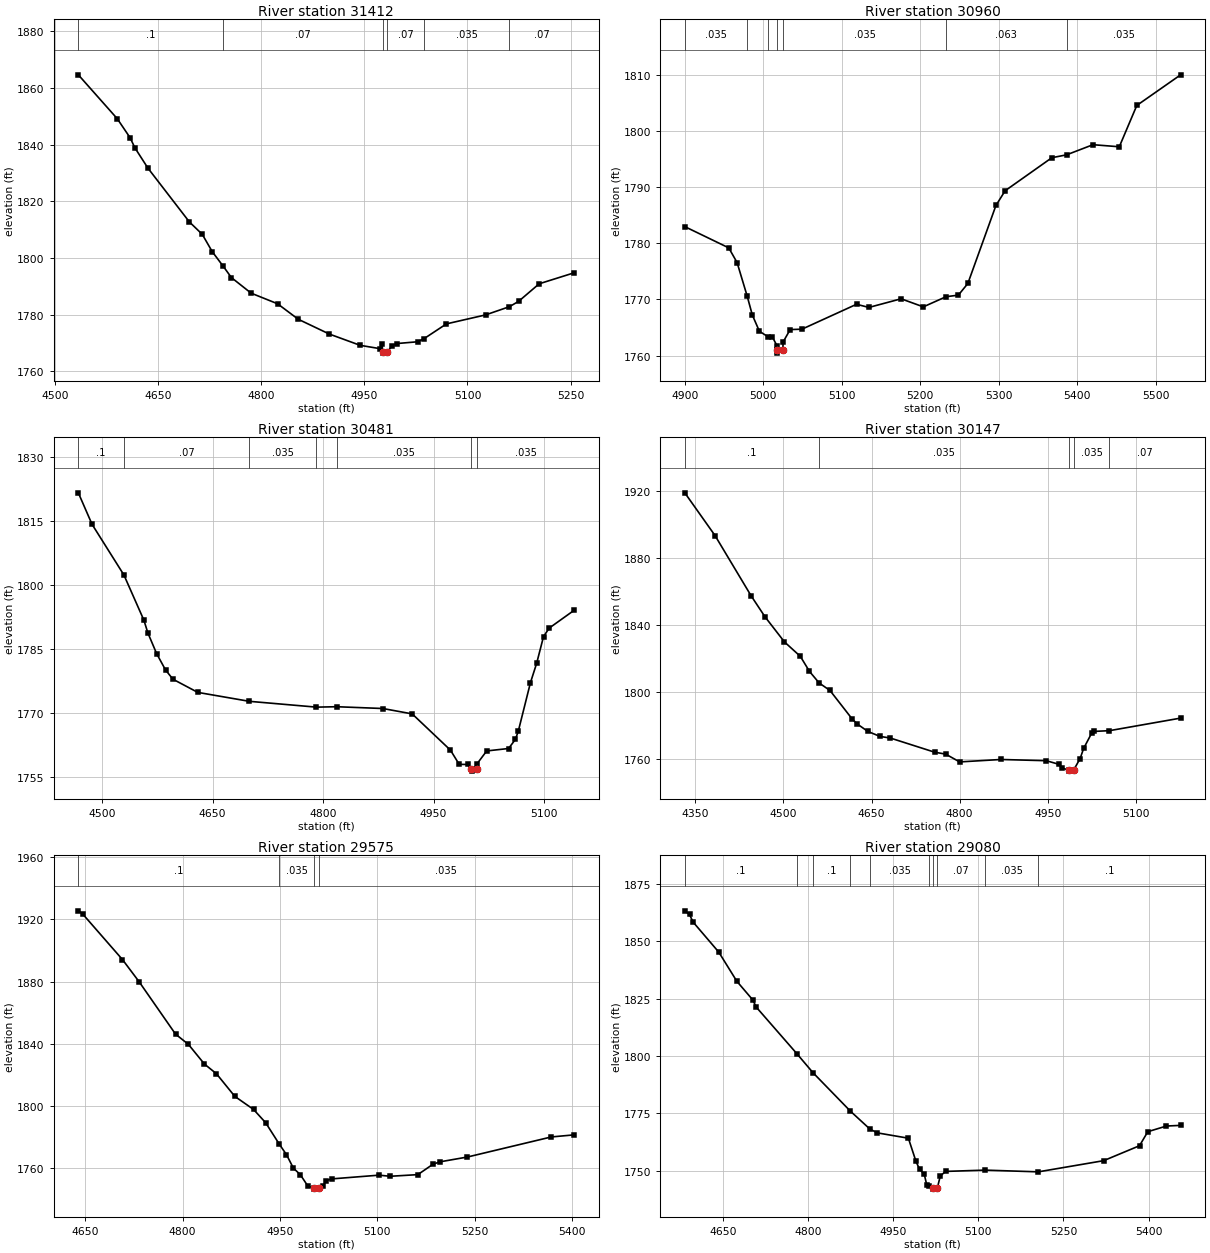
Type RM Length L Ch R = 1 ,31412   ,452,452,452
BEGIN DESCRIPTION:
Quinlan Creek 56.0
END DESCRIPTION:
XS GIS Cut Line= 3
      1939225.03     13940474.98        1938825.       13940725.
        1938825.     13940974.97
#Sta/Elev= 30
  4533.6 1864.66  4590.2 1849.18  4608.8  1842.5    4616 1838.86  4634.9 1831.71
  4695.2 1812.72    4714 1808.33  4728.5 1802.21  4744.4 1797.09  4756.4 1793.06
  4785.1 1787.56  4823.6 1783.81  4853.7 1778.34    4899 1773.11  4943.9 1769.13
  4972.2 1767.98  4975.8 1769.43  4976.5 1766.88    4977 1766.38  4983.5 1766.88
  4990.3 1768.93    4997 1769.76  5027.4 1770.39    5037 1771.52  5069.4 1776.71
  5126.4 1779.88  5161.1 1782.78  5174.4 1784.66  5204.4 1790.87  5255.3 1794.75
#Mann= 6 ,-1 , 0
  4533.6      .1       0  4744.4     .07       0  4976.5     .05       0
  4983.5     .07       0    5037    .035       0  5161.1     .07       0
Bank Sta=4976.5,4983.5
XS Rating Curve= 0 ,0
Exp/Cntr=0.3,0.1

Type RM Length L Ch R = 1 ,30960   ,479,479,479
BEGIN DESCRIPTION:
Quinlan Creek 55.0
END DESCRIPTION:
XS GIS Cut Line= 3
        1938425.     13940475.02        1938425.       13940575.
      1938074.99     13940975.01
#Sta/Elev= 30
  4900.1 1782.99  4956.1  1779.2  4966.7 1776.58  4979.5 1770.62  4986.1 1767.23
  4995.1 1764.33  5006.2 1763.34  5011.6 1763.33  5017.4 1761.77  5017.6 1760.93
  5018.1 1760.43  5025.1 1760.93  5025.2 1762.39  5034.3 1764.63  5049.3  1764.7
  5118.8 1769.14  5134.6 1768.58  5175.6 1770.12  5203.9 1768.68  5232.8 1770.49
  5248.5 1770.77  5260.6 1772.85  5296.4 1786.77  5308.1 1789.39  5367.6 1795.28
  5386.3 1795.79    5420  1797.6  5453.5 1797.23  5475.8  1804.6  5531.6 1810.06
#Mann= 7 ,-1 , 0
  4900.1    .035       0  4979.5     .07       0  5006.2    .035       0
  5017.6     .05       0  5025.1    .035       0  5232.8    .063       0
  5386.3    .035       0
Bank Sta=5017.6,5025.1
XS Rating Curve= 0 ,0
Exp/Cntr=0.3,0.1

Type RM Length L Ch R = 1 ,30481   ,334,334,334
BEGIN DESCRIPTION:
Quinlan Creek 54.0
END DESCRIPTION:
XS GIS Cut Line= 3
      1938324.99     13940175.01        1937975.       13940575.
      1937875.01     13940674.99
#Sta/Elev= 30
  4467.9 1821.51  4486.5 1814.15  4529.8 1802.29  4556.9 1791.72  4562.3 1788.74
  4574.2  1783.9  4586.2 1780.11  4596.3 1777.93    4630 1774.85    4700 1772.76
  4791.1  1771.4  4818.4  1771.5  4881.2 1771.08    4921 1769.82  4972.9 1761.35
  4984.8 1758.02  4997.2    1758  5001.3 1756.94  5001.8 1756.44  5008.9 1756.94
  5009.3 1758.22  5022.1 1761.16  5051.8 1761.73    5061 1763.85  5064.9 1765.72
  5081.5 1777.14  5089.9 1781.65  5099.2 1787.88  5106.9 1789.88  5140.8 1794.05
#Mann= 7 ,-1 , 0
  4467.9      .1       0  4529.8     .07       0    4700    .035       0
  4791.1     .07       0  4818.4    .035       0  5001.3    .035       0
  5008.9    .035       0
Bank Sta=5001.3,5008.9
XS Rating Curve= 0 ,0
Exp/Cntr=0.3,0.1

Type RM Length L Ch R = 1 ,30147   ,572,572,572
BEGIN DESCRIPTION:
Quinlan Creek 53.0
END DESCRIPTION:
XS GIS Cut Line= 3
      1938225.01     13939874.99      1937849.96     13940332.32
      1937600.08     13940367.52
#Sta/Elev= 30
  4332.2 1918.82  4383.6 1893.34  4445.1 1857.33  4468.7 1844.81  4501.8 1829.82
  4528.8 1821.22  4544.4 1812.22  4560.8 1805.33  4579.3 1800.83  4616.9 1783.89
  4625.8  1780.8  4643.8 1776.38  4664.6 1773.39  4681.6 1772.49  4757.3 1764.01
  4776.2 1762.85  4799.9  1758.2  4870.3 1759.65  4947.4 1758.92  4968.6 1756.81
  4974.7 1754.57    4986  1753.2  4986.5  1752.7  4993.7  1753.2    5005 1760.23
    5011  1766.3  5024.5 1775.29  5029.2 1776.42  5054.9 1776.85    5176 1784.35
#Mann= 5 ,-1 , 0
  4332.2      .1       0  4560.8    .035       0    4986    .035       0
  4993.7    .035       0  5054.9     .07       0
Bank Sta=4986,4993.7
XS Rating Curve= 0 ,0
Exp/Cntr=0.3,0.1

Type RM Length L Ch R = 1 ,29575   ,495,495,495
BEGIN DESCRIPTION:
Quinlan Creek 52.0
END DESCRIPTION:
XS GIS Cut Line= 3
      1938074.99     13939675.01        1937775.       13939875.
      1937574.98     13940225.04
#Sta/Elev= 30
  4639.5 1925.41  4646.2 1923.38  4707.5 1894.08  4733.3 1879.75  4789.2 1846.21
    4809 1839.64  4833.7 1826.99  4852.3 1820.72  4880.5 1806.22  4909.4 1797.81
    4928  1789.3    4949 1775.55  4960.1 1768.77  4970.7 1760.14  4981.5 1755.87
  4992.9 1748.67    5002 1747.13  5002.5 1746.63  5009.7 1747.13  5016.2  1748.4
    5021 1752.09    5030 1753.21  5102.6  1755.6  5119.9 1754.89  5162.4 1755.94
  5185.5 1762.55  5195.9 1764.12  5238.7 1767.25    5368 1780.15  5403.2 1781.49
#Mann= 4 ,-1 , 0
  4639.5      .1       0    4949    .035       0    5002    .035       0
  5009.7    .035       0
Bank Sta=5002,5009.7
XS Rating Curve= 0 ,0
Exp/Cntr=0.3,0.1

Type RM Length L Ch R = 1 ,29080   ,432,432,432
BEGIN DESCRIPTION:
Quinlan Creek 51.0
END DESCRIPTION:
XS GIS Cut Line= 3
        1937525.     13939125.02        1937425.       13939525.
      1937124.98     13939875.02
#Sta/Elev= 30
  4583.1 1863.17  4591.4  1861.6  4597.5 1858.34  4642.9 1845.21  4674.9 1832.47
  4702.7 1824.44  4708.9 1821.28  4780.3 1801.05  4808.8 1792.75  4874.9 1775.96
  4909.4 1768.14  4922.5 1766.53  4976.9 1764.22  4990.3 1754.11  4996.7 1750.64
  5004.7 1748.68  5009.3 1743.87  5013.6 1743.41    5020 1742.56  5020.5 1742.06
  5027.9 1742.56  5033.1 1747.77  5042.4 1749.77    5112 1750.33  5205.7 1749.58
  5320.8 1754.44    5384 1760.95  5398.6 1767.05  5431.4 1769.52  5456.4  1769.8
#Mann= 10 ,-1 , 0
  4583.1      .1       0  4780.3     .07       0  4808.8      .1       0
  4874.9     .07       0  4909.4    .035       0  5013.6     .07       0
    5020    .035       0  5027.9     .07       0    5112    .035       0
  5205.7      .1       0
Bank Sta=5020,5027.9
XS Rating Curve= 0 ,0
Exp/Cntr=0.3,0.1

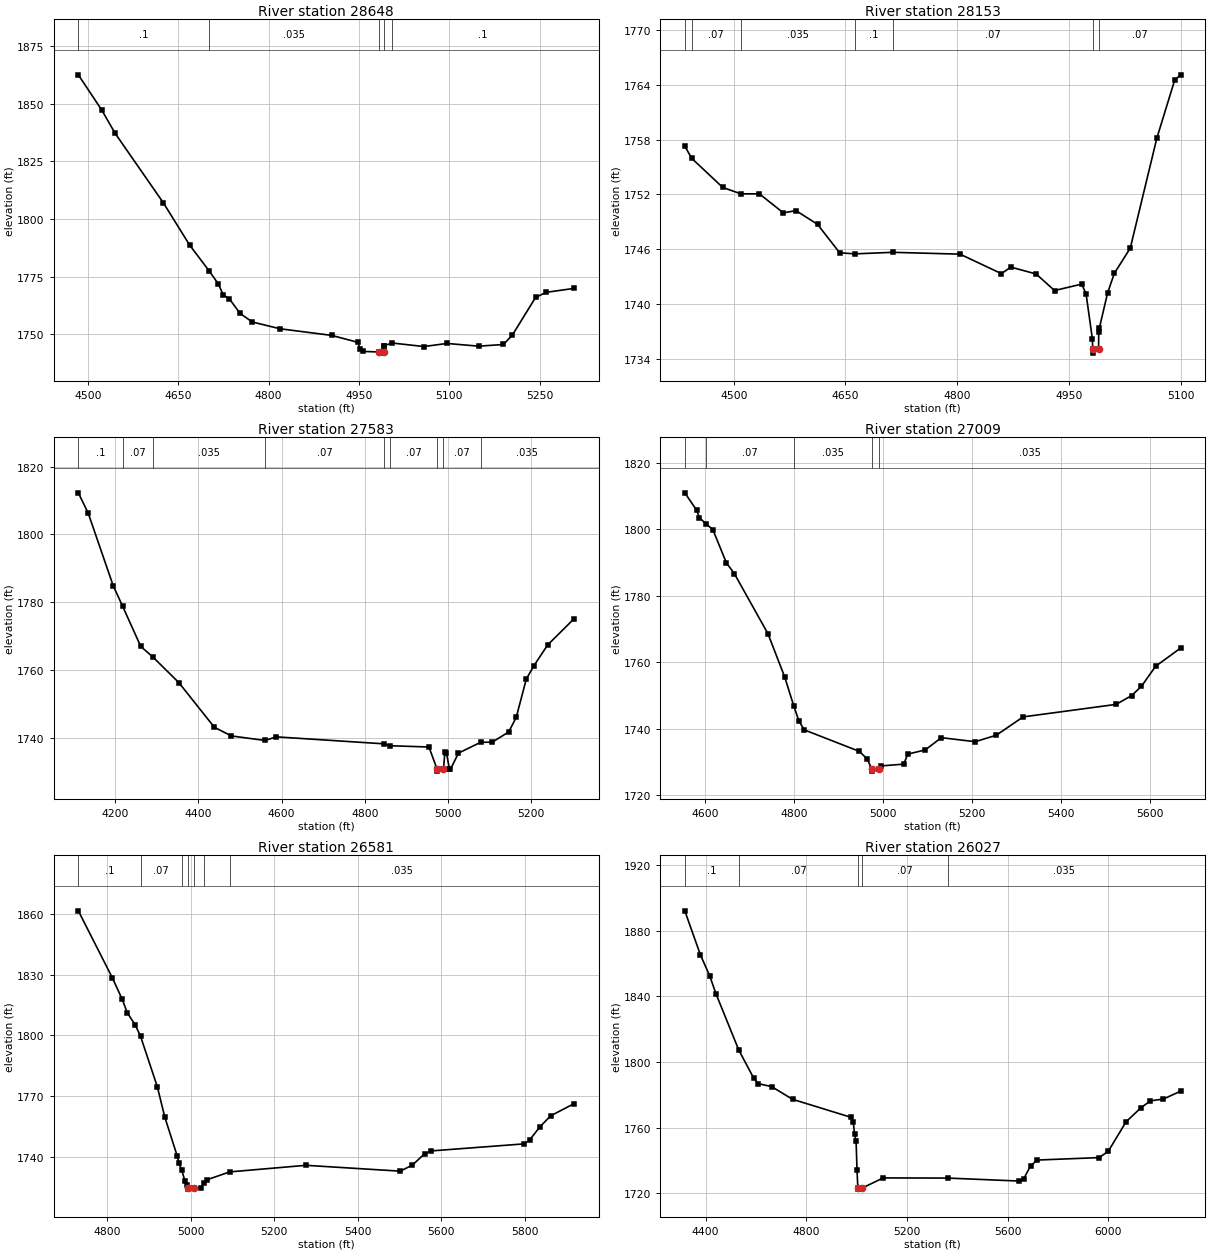
Type RM Length L Ch R = 1 ,28648   ,495,495,495
BEGIN DESCRIPTION:
Quinlan Creek 50.0
END DESCRIPTION:
XS GIS Cut Line= 3
      1937374.98     13939075.02        1937025.       13939475.
      1936875.01     13939724.98
#Sta/Elev= 30
  4484.2 1862.63    4523 1847.36  4545.3 1837.22  4625.1 1807.15  4668.9 1788.73
  4700.9 1777.64  4716.7 1771.79  4724.7 1767.09  4734.8 1765.42  4752.6 1759.05
    4773 1755.32  4819.1 1752.37  4904.8  1749.5    4948  1746.5  4951.9  1743.7
  4955.9 1742.55  4983.7  1742.3  4984.2  1741.8  4991.6  1742.3  4991.8  1744.9
  4992.2 1745.04  5004.8  1746.2  5057.7 1744.66  5096.2    1746  5148.7 1744.82
  5189.8 1745.55  5204.6 1749.61  5243.1 1765.96  5260.6 1768.19  5307.2 1769.91
#Mann= 5 ,-1 , 0
  4484.2      .1       0  4700.9    .035       0  4983.7    .035       0
  4991.6    .035       0  5004.8      .1       0
Bank Sta=4983.7,4991.6
XS Rating Curve= 0 ,0
Exp/Cntr=0.3,0.1

Type RM Length L Ch R = 1 ,28153   ,570,570,570
BEGIN DESCRIPTION:
Quinlan Creek 49.0
END DESCRIPTION:
XS GIS Cut Line= 3
      1936974.99     13939175.01        1936575.       13939575.
        1936575.     13939675.02
#Sta/Elev= 30
  4434.3 1757.29  4443.5 1755.96  4485.2 1752.77  4509.6 1752.07  4534.4 1752.07
  4566.6 1749.99  4583.6 1750.23  4612.5 1748.73  4642.2 1745.62  4662.8  1745.5
  4713.4 1745.67  4803.8 1745.47  4859.3 1743.34  4872.1 1744.05    4906  1743.3
  4930.7 1741.49  4967.2 1742.19  4973.1 1741.11  4981.6 1736.14  4981.9 1735.14
  4982.4 1734.64  4989.8 1735.14  4990.1 1736.99  4990.9 1737.39    5002 1741.24
    5011 1743.37  5032.4 1746.13    5068 1758.14    5092 1764.51    5100 1765.09
#Mann= 7 ,-1 , 0
  4434.3    .035       0  4443.5     .07       0  4509.6    .035       0
  4662.8      .1       0  4713.4     .07       0  4981.9     .05       0
  4989.8     .07       0
Bank Sta=4981.9,4989.8
XS Rating Curve= 0 ,0
Exp/Cntr=0.3,0.1

Type RM Length L Ch R = 1 ,27583   ,574,574,574
BEGIN DESCRIPTION:
Quinlan Creek 48.0
END DESCRIPTION:
XS GIS Cut Line= 3
      1937074.97     13938975.01      1936404.15     13939196.49
      1935924.97       13939275.
#Sta/Elev= 30
  4111.4 1812.28  4135.1 1806.29  4195.2 1784.86  4217.7 1778.85  4261.5 1766.92
  4290.1 1763.88  4353.1 1756.24  4438.4 1743.07  4479.5  1740.5  4560.7 1739.17
  4586.9 1740.24    4846 1738.18  4860.6 1737.62  4954.3 1737.24  4974.1 1730.62
  4974.6 1730.12  4989.2 1730.62  4992.6 1735.71  4996.2 1735.59  5003.5 1730.73
    5006 1730.66  5025.3 1735.44  5078.5 1738.63  5106.3 1738.67  5145.9 1741.66
  5164.1 1745.98  5188.4 1757.32  5206.7 1761.25  5239.8 1767.39  5303.4 1775.13
#Mann= 9 ,-1 , 0
  4111.4      .1       0  4217.7     .07       0  4290.1    .035       0
  4560.7     .07       0    4846    .035       0  4860.6     .07       0
  4974.1     .05       0  4989.2     .07       0  5078.5    .035       0
Bank Sta=4974.1,4989.2
XS Rating Curve= 0 ,0
Exp/Cntr=0.3,0.1

Type RM Length L Ch R = 1 ,27009   ,428,428,428
BEGIN DESCRIPTION:
Quinlan Creek 47.0
END DESCRIPTION:
XS GIS Cut Line= 3
      1937025.03       13938875.      1936452.89     13938801.39
      1935943.14     13938976.03
#Sta/Elev= 30
  4553.7 1810.98  4580.1  1805.8  4586.6 1803.49  4600.7 1801.75  4616.8 1799.93
  4647.1 1789.98  4665.2 1786.68  4740.8 1768.62  4778.4 1755.63  4798.7 1746.99
  4810.4 1742.39  4822.5  1739.7  4946.5 1733.23  4964.7 1730.87  4974.5 1727.79
    4975 1727.29  4989.7 1727.79  4995.5 1728.86  5046.3 1729.39  5055.4  1732.4
  5094.7 1733.67    5131 1737.35  5207.1 1736.14  5254.7 1738.09    5315  1743.6
  5524.3 1747.36  5559.1 1750.01  5581.3 1752.81  5613.1 1758.82  5669.4  1764.3
#Mann= 5 ,-1 , 0
  4553.7      .1       0  4600.7     .07       0  4798.7    .035       0
  4974.5    .035       0  4989.7    .035       0
Bank Sta=4974.5,4989.7
XS Rating Curve= 0 ,0
Exp/Cntr=0.3,0.1

Type RM Length L Ch R = 1 ,26581   ,554,554,554
BEGIN DESCRIPTION:
Quinlan Creek 46.0
END DESCRIPTION:
XS GIS Cut Line= 3
      1936944.63     13938426.89      1936666.31     13938420.34
      1935917.35     13938936.87
#Sta/Elev= 30
  4730.4  1861.4  4811.6 1828.53  4835.6  1817.8  4847.6 1811.24  4867.3 1804.98
  4879.6 1799.51  4919.6 1774.81  4937.6 1759.78  4967.7 1740.42  4971.5 1737.06
  4978.2 1733.65  4985.7 1728.46  4991.7  1726.4  4993.1 1724.81  4993.6 1724.31
  5008.3 1724.81  5024.4 1724.84  5030.7 1727.23  5038.2 1728.89  5093.2  1732.8
  5275.9 1736.04  5501.8 1733.16    5531 1736.16  5560.1 1741.72  5574.7 1743.11
  5797.9 1746.59  5811.6 1748.44  5836.7 1755.05  5862.6 1760.45  5918.6 1766.45
#Mann= 7 ,-1 , 0
  4730.4      .1       0  4879.6     .07       0  4978.2    .035       0
  4993.1    .035       0  5008.3    .035       0  5030.7     .07       0
  5093.2    .035       0
Bank Sta=4993.1,5008.3
XS Rating Curve= 0 ,0
Exp/Cntr=0.3,0.1

Type RM Length L Ch R = 1 ,26027   ,889,889,889
BEGIN DESCRIPTION:
Quinlan Creek 45.0
END DESCRIPTION:
XS GIS Cut Line= 3
      1936874.97     13937375.04      1936481.39     13937938.27
      1935724.97     13938975.04
#Sta/Elev= 30
  4317.2 1892.19  4379.4 1865.26    4416 1852.62  4441.6 1841.39  4531.8 1807.23
  4591.7 1789.93    4610 1786.72  4662.1 1784.97  4745.4 1777.22  4979.6 1766.14
  4986.8 1763.28    4992 1755.78  4997.9 1751.82  5001.6 1734.15    5005 1722.92
  5005.5 1722.42  5020.3 1722.92  5105.5 1729.26  5362.7 1729.16  5643.9 1727.36
  5664.2  1728.7  5691.2 1736.62  5718.3 1740.16  5963.9 1741.65  6000.2  1745.5
  6071.1 1763.55  6130.5 1772.09  6167.6 1776.27    6219 1777.37  6287.7 1782.18
#Mann= 5 ,-1 , 0
  4317.2      .1       0  4531.8     .07       0    5005     .05       0
  5020.3     .07       0  5362.7    .035       0
Bank Sta=5005,5020.3
XS Rating Curve= 0 ,0
Exp/Cntr=0.3,0.1

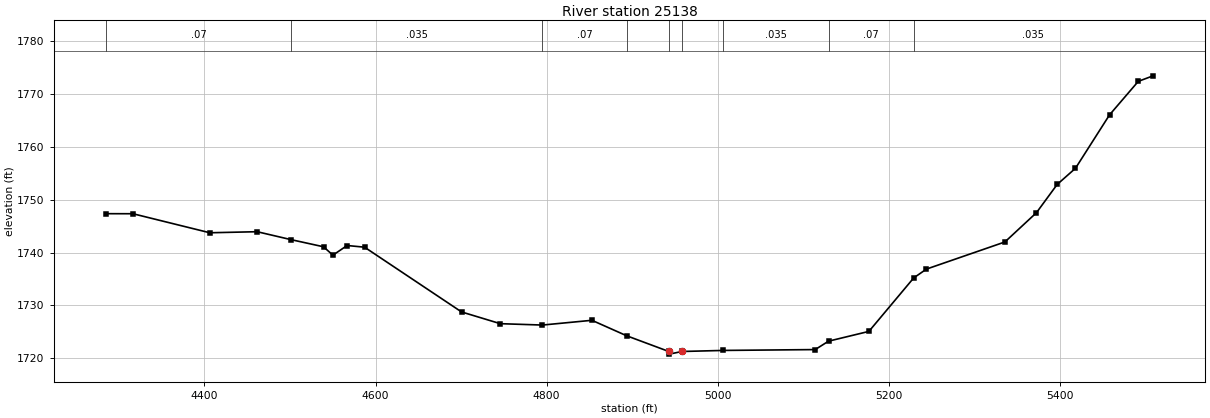
Type RM Length L Ch R = 1 ,25138   ,660,660,660
BEGIN DESCRIPTION:
Quinlan Creek 44.0
END DESCRIPTION:
XS GIS Cut Line= 3
      1936109.78     13937681.34      1935737.95      13938199.7
        1935625.     13938774.99
#Sta/Elev= 30
  4284.8 1747.36  4316.4 1747.35  4406.3 1743.75  4461.6 1743.95  4501.5 1742.44
  4539.2  1741.1  4550.2 1739.51  4566.8 1741.34  4587.2 1741.02  4700.6 1728.77
  4745.9 1726.55  4795.1 1726.29    4853 1727.19  4893.8 1724.25  4942.9 1721.29
  4943.4 1720.79  4958.3 1721.29  5006.7 1721.49    5114 1721.65  5129.6 1723.24
  5176.8 1725.09  5229.2 1735.21  5244.1 1736.88  5335.8 1742.01  5372.7 1747.55
  5396.9 1752.89  5418.3 1755.95  5458.1 1766.05  5491.7 1772.39    5509 1773.44
#Mann= 9 ,-1 , 0
  4284.8     .07       0  4501.5    .035       0  4795.1     .07       0
  4893.8    .033       0  4942.9    .033       0  4958.3    .033       0
  5006.7    .035       0  5129.6     .07       0  5229.2    .035       0
Bank Sta=4942.9,4958.3
XS Rating Curve= 0 ,0
Exp/Cntr=0.3,0.1