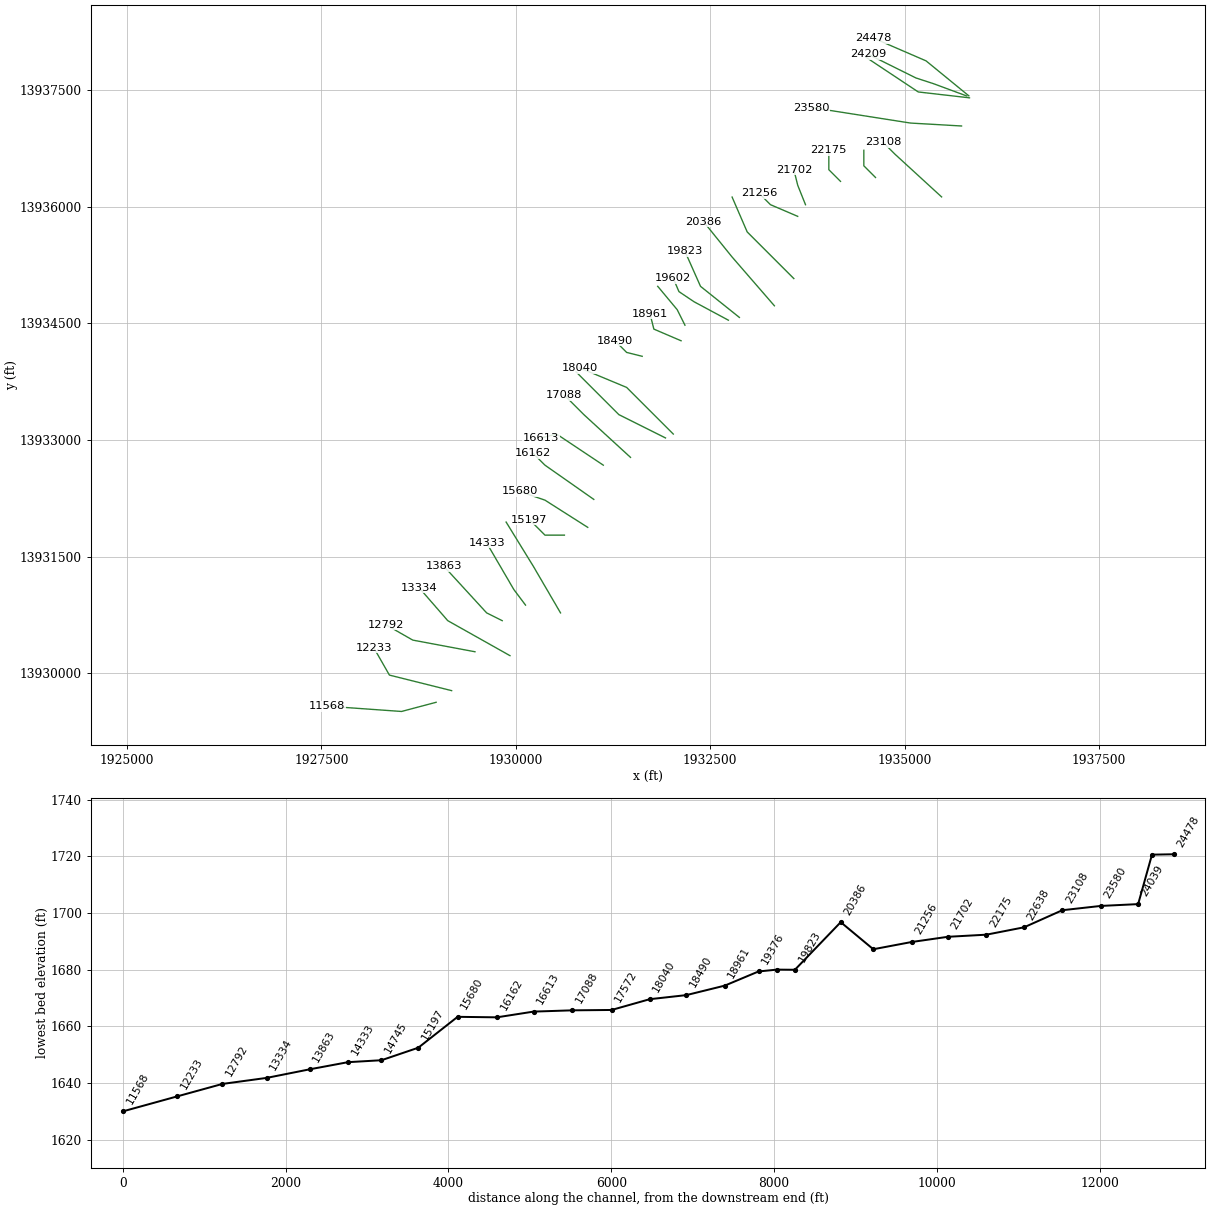
HEC-RAS study Quinlan Creek.prj: Quinlan Creek Base Level Engineering

--- Quinlan Creek.g01 (geometry) --- (continued)

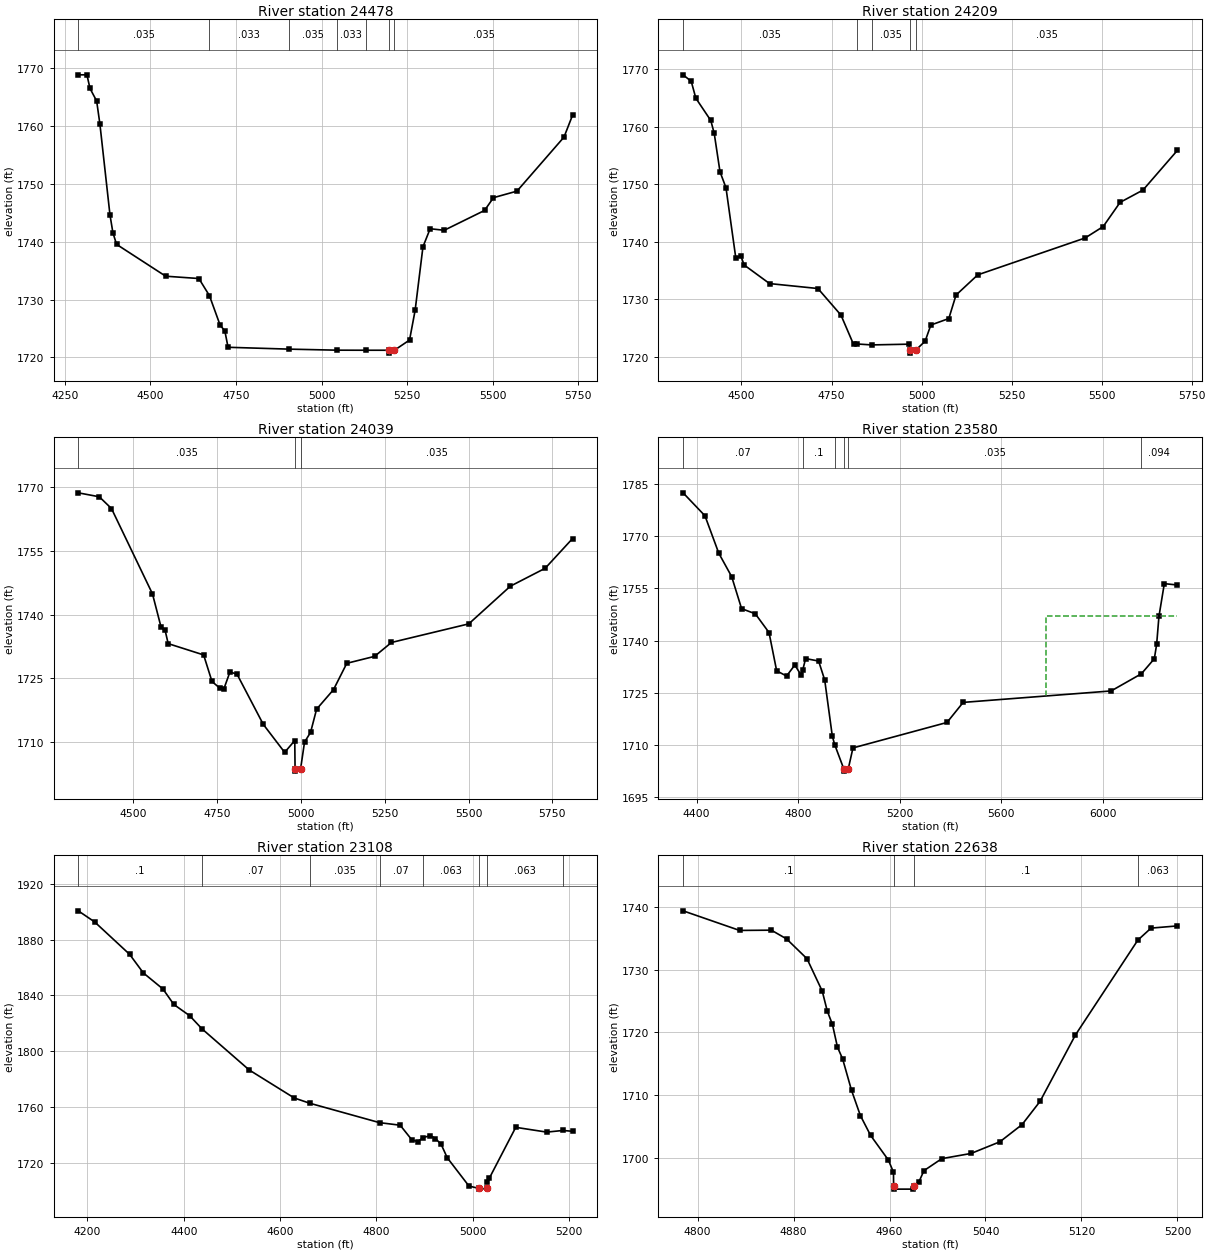
Type RM Length L Ch R = 1 ,24478   ,269,269,269
BEGIN DESCRIPTION:
Quinlan Creek 43.0
END DESCRIPTION:
XS GIS Cut Line= 3
        1935825.       13937425.        1935275.       13937875.
      1934602.42     13938165.82
#Sta/Elev= 30
  4289.6 1768.87  4314.9 1768.87  4323.9 1766.51  4343.3 1764.35  4352.8 1760.36
  4382.1  1744.7  4390.7 1741.59  4401.4 1739.56  4544.9 1734.05  4641.8 1733.65
  4672.6 1730.69  4703.8 1725.59  4717.6 1724.59    4727 1721.76  4905.8 1721.44
  5044.8 1721.26  5128.8 1721.25  5196.4 1721.25  5196.9 1720.75  5212.7 1721.25
  5256.9 1723.01  5273.2 1728.14  5296.1 1739.14  5317.1 1742.26  5358.1 1741.99
  5475.9 1745.42    5502 1747.63  5570.6 1748.76  5707.9  1758.1    5733 1761.91
#Mann= 7 ,-1 , 0
  4289.6    .035       0  4672.6    .033       0  4905.8    .035       0
  5044.8    .033       0  5128.8    .035       0  5196.4    .035       0
  5212.7    .035       0
Bank Sta=5196.4,5212.7
XS Rating Curve= 0 ,0
Exp/Cntr=0.3,0.1

Type RM Length L Ch R = 1 ,24209   ,170,170,170
BEGIN DESCRIPTION:
Quinlan Creek 42.1
END DESCRIPTION:
XS GIS Cut Line= 4
      1935798.61     13937423.24      1935368.89      13937582.1
      1935144.93     13937655.02       1934536.9     13937957.08
#Sta/Elev= 30
  4337.9 1769.07  4360.5 1767.94  4373.3    1765  4414.8 1761.12  4424.3  1758.9
  4440.4 1752.19    4457 1749.41  4484.4 1737.11    4498 1737.55  4507.6 1735.95
    4578 1732.72  4712.3 1731.86  4776.3 1727.23  4811.2 1722.13  4821.8  1722.2
  4861.4 1722.04  4965.8 1722.17  4967.1 1721.11  4967.6 1720.61  4983.5 1721.11
    5010 1722.69  5025.8  1725.5  5075.7 1726.63  5095.8 1730.72  5156.1 1734.24
  5454.2 1740.66  5504.4 1742.65  5551.3 1746.86    5615 1749.01  5710.5 1755.92
#Mann= 5 ,-1 , 0
  4337.9    .035       0  4821.8    .033       0  4861.4    .035       0
  4967.1    .035       0  4983.5    .035       0
Bank Sta=4967.1,4983.5
XS Rating Curve= 0 ,0
Exp/Cntr=0.3,0.1

Type RM Length L Ch R = 1 ,24039   ,459,459,459
BEGIN DESCRIPTION:
Quinlan Creek 42.0
END DESCRIPTION:
XS GIS Cut Line= 3
      1935833.75     13937399.33        1935175.       13937475.
      1934499.58     13937923.41
#Sta/Elev= 30
  4336.5 1768.64  4399.2 1767.71  4435.5 1764.95  4557.8 1744.86  4583.4 1737.03
  4595.5 1736.26  4604.6 1733.16  4710.3  1730.5  4735.2 1724.25  4758.6 1722.68
  4770.6  1722.5  4788.8  1726.5  4809.9 1725.96  4888.2 1714.15  4951.8 1707.58
    4982 1710.35  4982.9 1703.66  4983.4 1703.16  4999.3 1703.66  5011.1 1709.99
  5029.1 1712.28  5047.1 1717.74  5097.5 1722.33  5137.1 1728.53  5219.9 1730.16
  5270.3 1733.43  5500.8 1737.81  5624.7 1746.67  5728.6 1750.89  5810.3 1757.89
#Mann= 3 ,-1 , 0
  4336.5    .035       0  4982.9    .035       0  4999.3    .035       0
Bank Sta=4982.9,4999.3
XS Rating Curve= 0 ,0
Exp/Cntr=0.3,0.1

Type RM Length L Ch R = 1 ,23580   ,472,472,472
BEGIN DESCRIPTION:
Quinlan Creek 41.0
END DESCRIPTION:
XS GIS Cut Line= 3
      1935731.52     13937037.31        1935075.       13937075.
      1933800.49       13937275.
#Sta/Elev= 30
  4346.9 1782.41  4433.1 1775.82  4487.5 1765.08  4538.3 1758.36  4577.4 1749.16
  4631.4 1747.69  4685.5  1742.3  4715.6 1731.31  4754.6 1729.82  4787.2 1732.99
  4811.7 1730.09  4817.9 1731.45  4829.8 1734.83  4880.9 1734.12  4904.9 1728.68
  4934.9 1712.55  4944.4 1710.09  4980.8 1703.02  4981.3 1702.52  4997.3 1703.02
  5016.2 1709.18  5386.7 1716.49  5450.4 1722.25  6033.5 1725.54  6152.7 1730.47
  6203.6 1734.78  6212.7 1738.88  6221.8 1746.93    6243 1756.34  6294.6 1755.95
#Mann= 6 ,-1 , 0
  4346.9     .07       0  4817.9      .1       0  4944.4    .035       0
  4980.8    .035       0  4997.3    .035       0  6152.7    .094       0
#XS Ineff= 2 , 0
                         5778.22         1746.91
Permanent Ineff=
       F       F
Bank Sta=4980.8,4997.3
XS Rating Curve= 0 ,0
Exp/Cntr=0.3,0.1

Type RM Length L Ch R = 1 ,23108   ,470,470,470
BEGIN DESCRIPTION:
Quinlan Creek 40.0
END DESCRIPTION:
XS GIS Cut Line= 3
      1935475.01     13936124.99        1934875.       13936675.
        1934725.       13936825.
#Sta/Elev= 30
  4181.1  1900.7  4215.2 1892.71  4287.7 1869.48  4316.2 1856.14  4356.9  1844.6
  4379.5  1833.5  4412.3 1825.46  4437.9 1816.03  4535.9 1786.52  4629.5  1766.4
  4661.5 1762.65  4806.5 1748.71  4849.3 1746.87  4873.7 1736.31  4885.9 1735.12
  4896.8 1737.97  4912.2 1739.43  4922.6 1737.33  4934.4 1733.12    4947 1723.53
  4992.1 1703.21  5013.3 1701.51  5013.8 1701.01    5030 1701.51  5030.5 1705.81
  5034.4 1708.87  5089.2 1745.35  5153.5 1741.92  5187.2  1743.1  5207.2  1742.5
#Mann= 8 ,-1 , 0
  4181.1      .1       0  4437.9     .07       0  4661.5    .035       0
  4806.5     .07       0  4896.8    .063       0  5013.3     .05       0
    5030    .063       0  5187.2    .035       0
Bank Sta=5013.3,5030
XS Rating Curve= 0 ,0
Exp/Cntr=0.3,0.1

Type RM Length L Ch R = 1 ,22638   ,463,463,463
BEGIN DESCRIPTION:
Quinlan Creek 39.0
END DESCRIPTION:
XS GIS Cut Line= 3
      1934624.98     13936375.02        1934475.       13936525.
        1934475.     13936724.99
#Sta/Elev= 30
  4787.9 1739.43    4835  1736.3  4861.5 1736.34  4874.2 1734.94  4891.2 1731.78
  4903.9 1726.61  4908.1 1723.42  4912.4 1721.29  4916.6 1717.66  4920.9 1715.78
  4928.3 1710.77  4935.7 1706.73  4944.2 1703.57    4959 1699.64  4963.3 1697.68
  4963.4 1695.48  4963.9 1694.98  4979.7 1694.98  4980.2 1695.48  4984.5 1696.14
  4988.7 1697.93  5003.6 1699.85    5028 1700.68    5052 1702.54  5070.5 1705.29
  5085.5    1709    5115 1719.61    5167 1734.75    5178 1736.67    5200 1737.02
#Mann= 4 ,-1 , 0
  4787.9      .1       0  4963.4    .035       0  4980.2      .1       0
    5167    .063       0
Bank Sta=4963.4,4980.2
XS Rating Curve= 0 ,0
Exp/Cntr=0.3,0.1

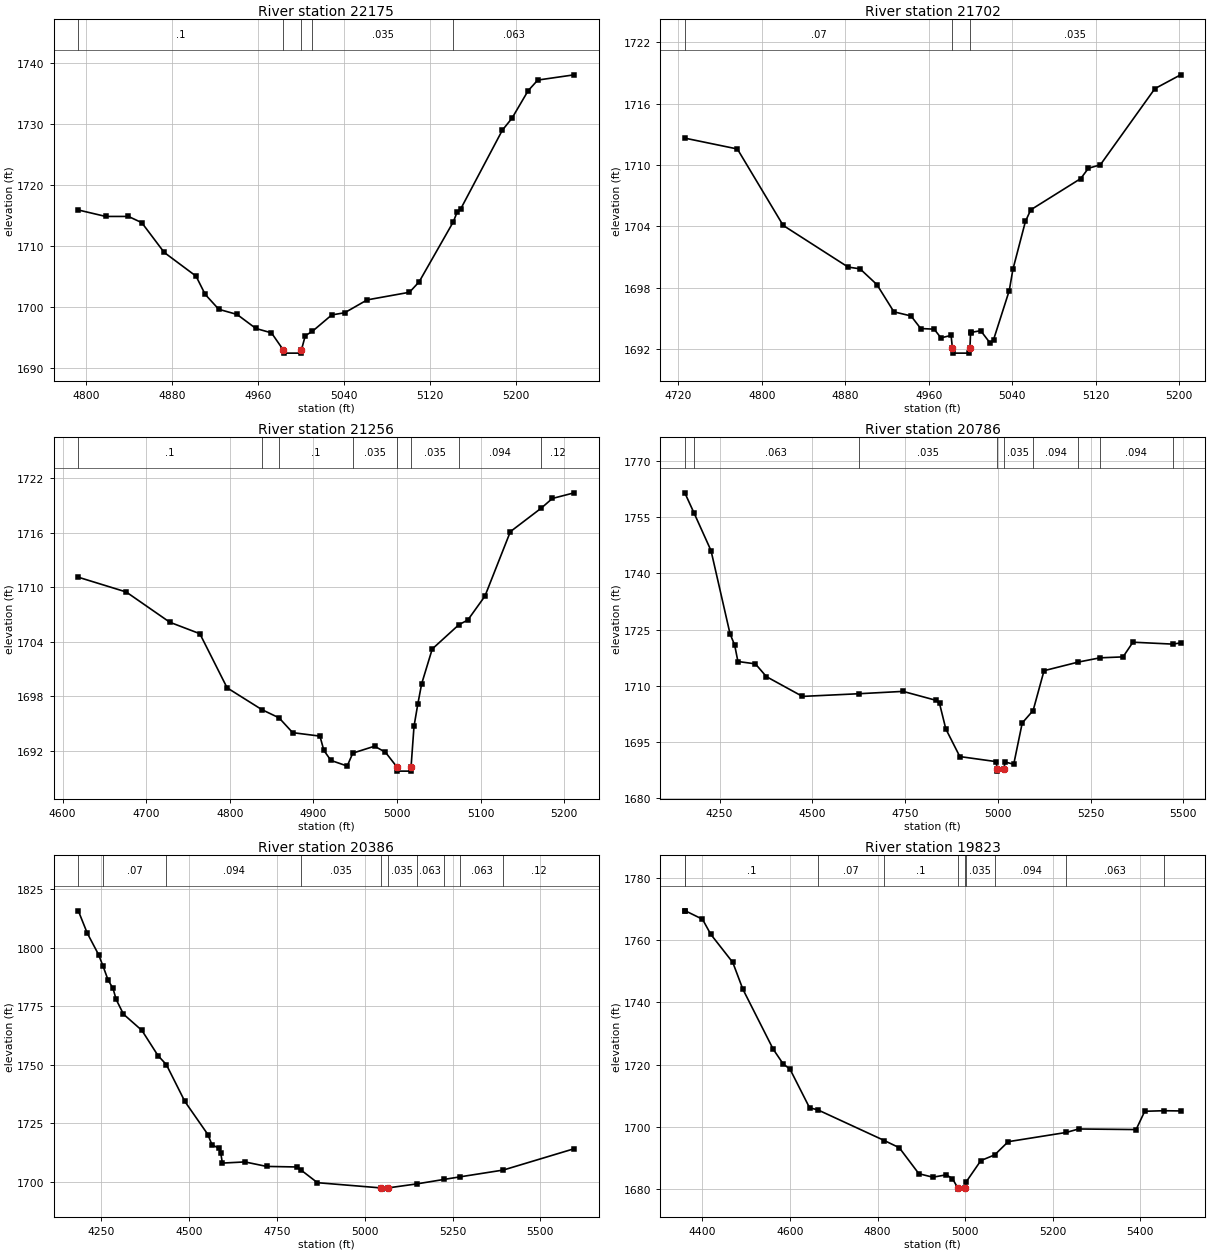
Type RM Length L Ch R = 1 ,22175   ,473,473,473
BEGIN DESCRIPTION:
Quinlan Creek 38.0
END DESCRIPTION:
XS GIS Cut Line= 3
        1934175.       13936325.        1934025.       13936475.
        1934025.     13936724.96
#Sta/Elev= 30
  4792.4  1715.9  4817.9 1714.84  4839.1 1714.84  4851.5 1713.82  4872.4 1708.93
  4902.1 1705.03  4910.6 1702.04  4923.3 1699.58  4940.3 1698.74  4957.9 1696.43
  4972.4 1695.71  4983.5 1692.88    4984 1692.38  4999.8 1692.38  5000.3 1692.88
  5003.9 1695.24  5010.5 1695.96  5028.6 1698.66  5040.6 1699.01  5061.6 1701.13
    5101 1702.38    5110 1704.09  5141.9 1713.96  5145.6 1715.64  5148.6 1716.02
  5187.6 1729.02  5196.6 1730.99  5211.6  1735.5  5220.6 1737.25  5254.5 1738.11
#Mann= 5 ,-1 , 0
  4792.4      .1       0  4983.5     .05       0  5000.3      .1       0
  5010.5    .035       0  5141.9    .063       0
Bank Sta=4983.5,5000.3
XS Rating Curve= 0 ,0
Exp/Cntr=0.3,0.1

Type RM Length L Ch R = 1 ,21702   ,446,446,446
BEGIN DESCRIPTION:
Quinlan Creek 37.0
END DESCRIPTION:
XS GIS Cut Line= 3
      1933724.99     13936025.02        1933625.       13936275.
        1933575.       13936475.
#Sta/Elev= 30
  4726.1 1712.62  4776.5 1711.56  4820.4  1704.1  4882.7 1700.03  4894.1 1699.86
  4910.3 1698.32  4926.6 1695.66    4943 1695.26  4952.3 1694.03  4965.2 1693.97
  4971.7 1693.12  4981.4 1693.36  4982.7 1692.13  4983.2 1691.63    4999 1691.63
  4999.5 1692.13  5000.1 1693.61  5000.5 1693.65  5009.8 1693.82  5019.1 1692.58
  5022.2 1692.96  5037.2 1697.74  5040.7 1699.81  5052.7 1704.49  5057.8 1705.62
  5105.7 1708.67  5113.1 1709.68  5124.5 1710.01  5176.8 1717.45  5201.5  1718.8
#Mann= 3 ,-1 , 0
  4726.1     .07       0  4982.7    .035       0  4999.5    .035       0
Bank Sta=4982.7,4999.5
XS Rating Curve= 0 ,0
Exp/Cntr=0.3,0.1

Type RM Length L Ch R = 1 ,21256   ,470,470,470
BEGIN DESCRIPTION:
Quinlan Creek 36.0
END DESCRIPTION:
XS GIS Cut Line= 3
      1933624.98     13935875.01        1933275.       13936025.
        1933125.       13936175.
#Sta/Elev= 30
  4618.8 1711.11    4676 1709.49  4728.2 1706.16  4764.1  1704.9  4796.7 1698.95
  4838.3 1696.55  4858.8 1695.65  4875.1 1694.02  4907.7 1693.64  4912.4 1692.07
  4920.8 1690.97  4940.3 1690.35    4947 1691.77    4973 1692.53    4986 1691.87
  4999.4 1690.29  4999.9 1689.79  5016.2 1689.79  5016.7 1690.29  5020.2 1694.72
  5024.7 1697.14  5029.3 1699.38    5042 1703.22    5074  1705.9  5084.5  1706.4
    5105 1709.03  5135.4 1716.12  5172.4 1718.71  5185.6 1719.77  5211.7 1720.39
#Mann= 8 ,-1 , 0
  4618.8      .1       0  4838.3     .07       0  4858.8      .1       0
    4947    .035       0  4999.4    .035       0  5016.7    .035       0
    5074    .094       0  5172.4     .12       0
Bank Sta=4999.4,5016.7
XS Rating Curve= 0 ,0
Exp/Cntr=0.3,0.1

Type RM Length L Ch R = 1 ,20786   ,400,400,400
BEGIN DESCRIPTION:
Quinlan Creek 35.0
END DESCRIPTION:
XS GIS Cut Line= 3
      1933574.99     13935075.01        1932975.       13935675.
      1932781.31     13936123.01
#Sta/Elev= 30
  4156.3 1761.47  4181.7 1755.98    4227 1746.05  4278.3 1723.85  4290.7 1720.87
  4299.5 1716.48  4346.6 1715.85  4376.3 1712.44  4473.5 1707.17  4624.7 1707.88
  4744.6 1708.51  4834.1 1706.11    4843 1705.28  4859.9  1698.5  4897.7 1691.12
  4995.3 1689.78  4998.4 1687.74  4998.9 1687.24  5015.7 1687.74  5020.1 1689.66
    5043 1689.08  5065.9 1700.09  5095.3 1703.41  5124.7 1714.03  5216.7 1716.32
  5275.4 1717.46  5337.7 1717.71  5364.3 1721.63  5471.2 1721.12  5492.9 1721.43
#Mann= 9 ,-1 , 0
  4156.3    .035       0  4181.7    .063       0  4624.7    .035       0
  4998.4    .035       0  5015.7    .035       0  5095.3    .094       0
  5216.7     .12       0  5275.4    .094       0  5471.2     .12       0
Bank Sta=4998.4,5015.7
XS Rating Curve= 0 ,0
Exp/Cntr=0.3,0.1

Type RM Length L Ch R = 1 ,20386   ,563,563,563
BEGIN DESCRIPTION:
Quinlan Creek 34.0
END DESCRIPTION:
XS GIS Cut Line= 3
      1933325.03     13934724.97      1932782.12     13935350.96
      1932416.12     13935803.96
#Sta/Elev= 30
  4185.1 1815.75  4210.3 1806.28  4242.5 1797.08  4255.8 1791.97  4269.9  1786.1
  4283.7 1782.62  4292.8 1777.85  4313.6 1771.57  4366.1 1764.62  4411.9 1753.84
  4435.6 1750.01  4488.3 1734.25  4553.8 1720.12  4565.5 1715.73  4585.9  1714.2
  4590.5 1712.13    4595 1707.92  4659.1 1708.42  4720.8  1706.5    4806 1706.26
  4817.9 1705.05  4865.6 1699.54  5047.6 1697.29  5048.1 1696.79  5065.3 1697.29
    5148 1699.02  5225.9 1700.94  5271.3 1702.04  5394.5 1704.95  5596.1 1714.06
#Mann= 10 ,-1 , 0
  4185.1      .1       0  4255.8     .07       0  4435.6    .094       0
  4817.9    .035       0  5047.6    .035       0  5065.3    .035       0
    5148    .063       0  5225.9    .035       0  5271.3    .063       0
  5394.5     .12       0
Bank Sta=5047.6,5065.3
XS Rating Curve= 0 ,0
Exp/Cntr=0.3,0.1

Type RM Length L Ch R = 1 ,19823   ,221,221,221
BEGIN DESCRIPTION:
Quinlan Creek 33.0
END DESCRIPTION:
XS GIS Cut Line= 3
      1932874.99     13934575.01        1932375.       13934975.
      1932175.02     13935424.96
#Sta/Elev= 30
  4359.7 1769.34    4361 1769.34  4400.1 1766.64    4419 1761.81  4469.3 1752.78
  4492.3 1744.19  4561.5 1724.96  4584.5 1720.17  4599.9 1718.55  4644.7 1706.12
  4663.9 1705.43  4815.3 1695.61  4849.6  1693.3  4894.4 1684.95  4926.4 1683.83
    4957 1684.59  4971.2 1683.37  4982.8  1680.5  4983.3    1680  5000.6  1680.5
  5002.2 1682.27  5036.1 1689.17  5067.5 1690.98  5098.5 1695.23  5231.3  1698.2
  5259.4 1699.31  5390.7 1699.12  5410.4 1704.99  5453.3 1705.17  5492.4  1705.1
#Mann= 10 ,-1 , 0
  4359.7     .07       0    4361      .1       0  4663.9     .07       0
  4815.3      .1       0  4982.8     .05       0  5000.6      .1       0
  5002.2    .035       0  5067.5    .094       0  5231.3    .063       0
  5453.3    .094       0
Bank Sta=4982.8,5000.6
XS Rating Curve= 0 ,0
Exp/Cntr=0.3,0.1

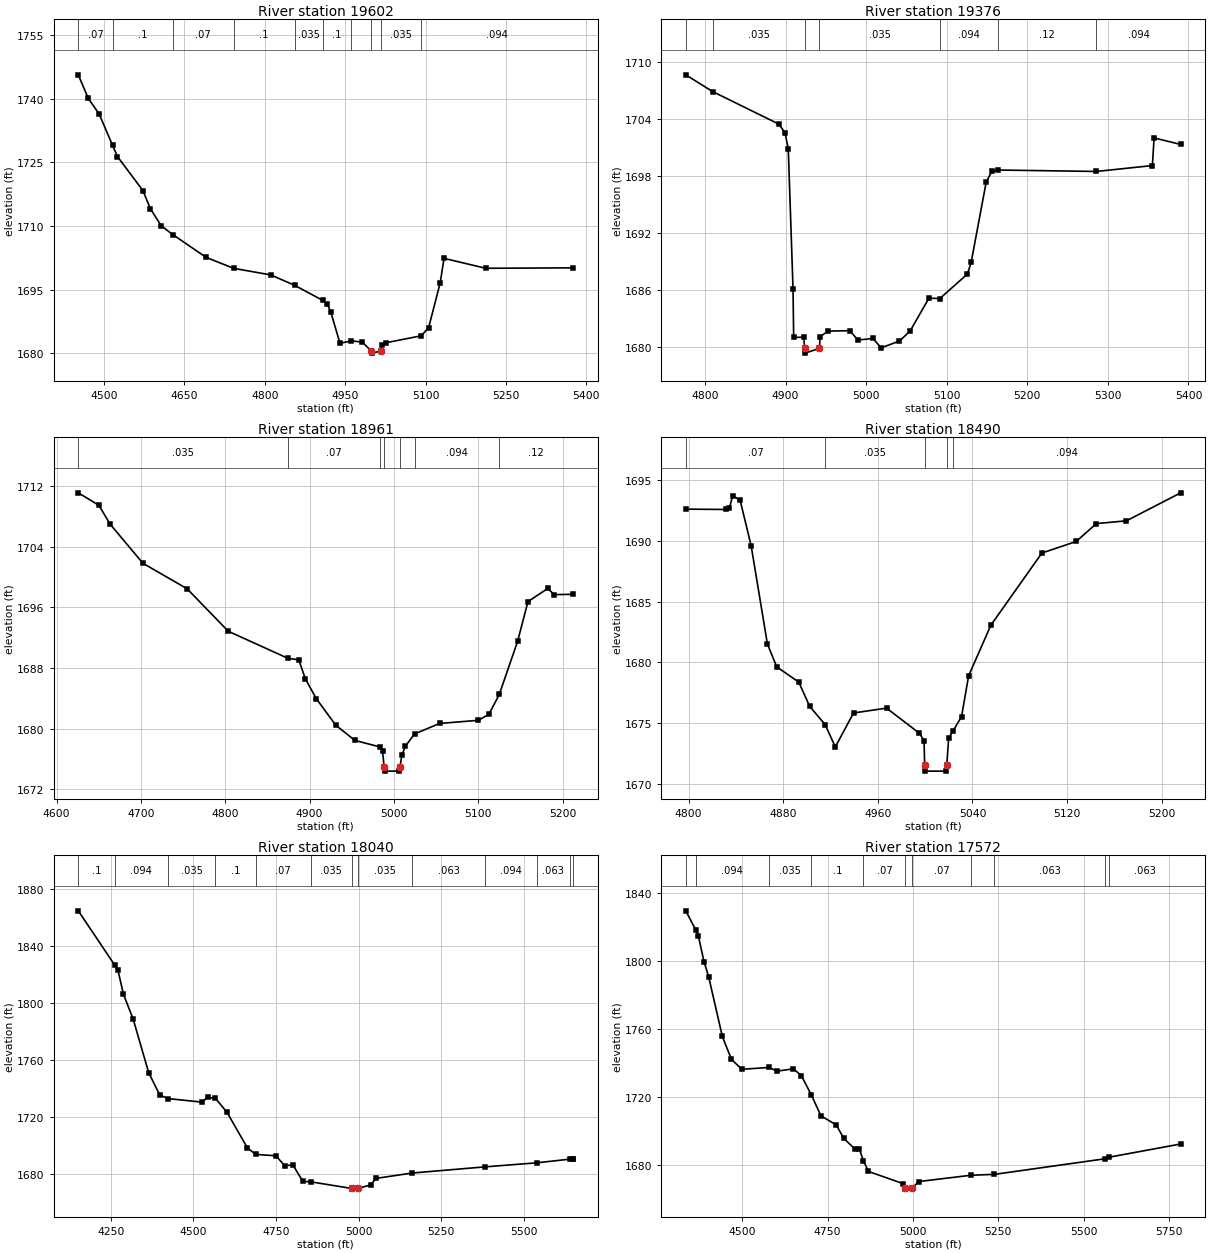
Type RM Length L Ch R = 1 ,19602   ,226,226,226
BEGIN DESCRIPTION:
Mapping XS df514881
END DESCRIPTION:
XS GIS Cut Line= 4
      1932733.86     13934539.38       1932292.3     13934776.51
      1932097.46     13934907.34      1932023.78     13935080.41
#Sta/Elev= 30
  4451.7 1745.65  4470.3 1740.11  4490.8 1736.38  4515.6 1729.05  4524.8 1726.39
  4572.5 1718.34  4586.2 1714.11  4606.5 1710.08  4627.9 1708.01  4690.3 1702.63
  4741.7 1700.04  4810.9 1698.49  4855.6 1696.04  4908.1 1692.48  4916.3 1691.73
  4923.2  1689.7  4940.3 1682.37  4961.8 1682.94    4982 1682.64  4998.7 1680.55
  4999.2 1680.05  5017.2 1680.55  5018.4 1681.97  5026.2  1682.5  5091.9 1684.13
  5105.7 1686.01  5127.4 1696.61  5134.6 1702.39  5212.3 1700.05  5375.7 1700.15
#Mann= 10 ,-1 , 0
  4451.7     .07       0  4515.6      .1       0  4627.9     .07       0
  4741.7      .1       0  4855.6    .035       0  4908.1      .1       0
  4961.8    .035       0  4998.7    .035       0  5017.2    .035       0
  5091.9    .094       0
Bank Sta=4998.7,5017.2
XS Rating Curve= 0 ,0
Exp/Cntr=0.3,0.1

Type RM Length L Ch R = 1 ,19376   ,415,415,415
BEGIN DESCRIPTION:
Quinlan Creek 32.0
END DESCRIPTION:
XS GIS Cut Line= 3
      1932175.02     13934474.96        1932075.       13934675.
      1931824.98     13934975.03
#Sta/Elev= 30
  4776.1 1708.69  4809.4 1706.93  4891.4 1703.51  4899.2 1702.61  4903.3 1700.91
  4909.2 1686.18    4910 1681.05  4922.6 1681.08  4923.5  1679.9    4924  1679.4
    4942  1679.9  4942.8 1681.13  4952.8 1681.72  4979.7 1681.76  4989.7 1680.78
  5008.4 1680.94  5018.6 1679.96  5041.2 1680.67  5054.5 1681.72  5077.9 1685.19
  5091.3 1685.14  5125.6 1687.72  5130.3 1688.96    5149 1697.43    5156 1698.53
  5164.1 1698.67  5285.6 1698.52  5355.2 1699.14  5357.3 1702.05  5390.3 1701.36
#Mann= 7 ,-1 , 0
  4776.1    .094       0  4809.4    .035       0  4923.5    .035       0
    4942    .035       0  5091.3    .094       0  5164.1     .12       0
  5285.6    .094       0
Bank Sta=4923.5,4942
XS Rating Curve= 0 ,0
Exp/Cntr=0.3,0.1

Type RM Length L Ch R = 1 ,18961   ,471,471,471
BEGIN DESCRIPTION:
Quinlan Creek 31.0
END DESCRIPTION:
XS GIS Cut Line= 3
      1932124.96     13934275.02        1931775.       13934425.
        1931725.       13934625.
#Sta/Elev= 30
  4625.7 1711.08  4650.2 1709.43  4663.3 1706.97  4702.4 1701.79  4754.7 1698.44
  4803.6 1692.83  4874.3 1689.27  4887.2 1689.07  4895.1 1686.53  4908.1 1683.93
  4930.9 1680.47  4953.7 1678.45    4983  1677.6  4986.5    1677  4988.5  1674.9
    4989  1674.4  5006.6  1674.4  5007.1  1674.9  5009.4 1676.47  5013.7 1677.71
  5024.5  1679.3  5054.1 1680.68  5100.3  1681.1  5112.7  1681.9    5125 1684.52
  5146.7 1691.51    5159 1696.75  5182.6 1698.48    5190 1697.66  5212.6 1697.71
#Mann= 7 ,-1 , 0
  4625.7    .035       0  4874.3     .07       0    4983    .035       0
  4988.5    .035       0  5007.1    .035       0  5024.5    .094       0
    5125     .12       0
Bank Sta=4988.5,5007.1
XS Rating Curve= 0 ,0
Exp/Cntr=0.3,0.1

Type RM Length L Ch R = 1 ,18490   ,450,450,450
BEGIN DESCRIPTION:
Quinlan Creek 30.0
END DESCRIPTION:
XS GIS Cut Line= 3
      1931625.04     13934074.99        1931425.       13934125.
      1931275.02     13934274.98
#Sta/Elev= 30
  4797.7  1692.6  4831.3 1692.57  4834.4 1692.66  4837.5 1693.72  4843.7 1693.31
    4853 1689.56  4866.7 1681.51  4874.6 1679.63  4893.2 1678.38  4902.4 1676.39
  4915.5 1674.88  4924.1 1673.05  4939.5 1675.84  4967.4 1676.24  4995.2 1674.17
  4999.1 1673.55  4999.6 1671.56  5000.1 1671.06  5017.8 1671.06  5018.3 1671.56
  5019.9 1673.78  5023.7 1674.37  5030.8 1675.55  5036.8 1678.91  5055.6 1683.06
  5098.7 1688.99  5127.7 1689.94  5144.7 1691.41  5170.2 1691.64    5216 1693.94
#Mann= 5 ,-1 , 0
  4797.7     .07       0  4915.5    .035       0  4999.6    .035       0
  5018.3    .035       0  5023.7    .094       0
Bank Sta=4999.6,5018.3
XS Rating Curve= 0 ,0
Exp/Cntr=0.3,0.1

Type RM Length L Ch R = 1 ,18040   ,468,468,468
BEGIN DESCRIPTION:
Quinlan Creek 29.0
END DESCRIPTION:
XS GIS Cut Line= 3
      1932024.98     13933075.02        1931425.       13933675.
        1930825.       13933925.
#Sta/Elev= 30
  4151.4 1864.51  4261.2 1826.66  4271.2  1823.3  4288.1 1806.13  4317.8 1788.52
  4364.5 1751.22    4398 1735.55  4422.7 1733.03  4525.7 1730.55  4542.7 1733.86
  4566.7 1733.22  4601.7 1723.44  4663.2 1698.58  4688.7 1693.93  4750.1 1692.98
    4776 1686.02  4801.5 1686.56  4831.2 1675.02  4854.7 1674.76  4978.7 1670.12
  4979.2 1669.62  4997.7 1670.12  5036.4 1672.51  5052.7 1677.13  5162.2 1680.89
  5382.9 1685.21  5540.2 1688.06  5639.5  1690.6  5648.5 1690.86  5649.9 1690.97
#Mann= 13 ,-1 , 0
  4151.4      .1       0  4261.2    .094       0  4422.7    .035       0
  4566.7      .1       0  4688.7     .07       0  4854.7    .035       0
  4978.7    .035       0  4997.7    .035       0  5162.2    .063       0
  5382.9    .094       0  5540.2    .063       0  5639.5    .094       0
  5648.5    .063       0
Bank Sta=4978.7,4997.7
XS Rating Curve= 0 ,0
Exp/Cntr=0.3,0.1

Type RM Length L Ch R = 1 ,17572   ,484,484,484
BEGIN DESCRIPTION:
Quinlan Creek 28.0
END DESCRIPTION:
XS GIS Cut Line= 3
      1931925.01     13933024.99        1931325.       13933325.
      1930775.04     13933874.96
#Sta/Elev= 30
  4335.1 1829.76  4364.9 1818.24  4371.7 1815.16  4388.4 1799.85  4401.9 1791.06
  4442.1 1755.75  4468.9 1742.24  4499.1 1736.41  4578.1 1737.48  4603.1 1735.34
  4650.1 1736.69  4673.5 1732.65    4703 1721.18  4730.6 1709.02  4775.8 1703.61
  4797.6 1695.66  4831.2 1689.29  4842.9 1689.58  4854.9 1682.65  4869.8 1676.24
  4970.4  1669.1  4977.6 1666.32  4978.1 1665.82  4996.7 1666.32  5017.4  1670.3
  5170.2    1674  5238.2 1674.51  5562.5 1683.71  5574.6 1684.65  5783.7  1692.4
#Mann= 11 ,-1 , 0
  4335.1    .035       0  4364.9    .094       0  4578.1    .035       0
    4703      .1       0  4854.9     .07       0  4977.6     .05       0
  4996.7     .07       0  5170.2    .035       0  5238.2    .063       0
  5562.5    .094       0  5574.6    .063       0
Bank Sta=4977.6,4996.7
XS Rating Curve= 0 ,0
Exp/Cntr=0.3,0.1

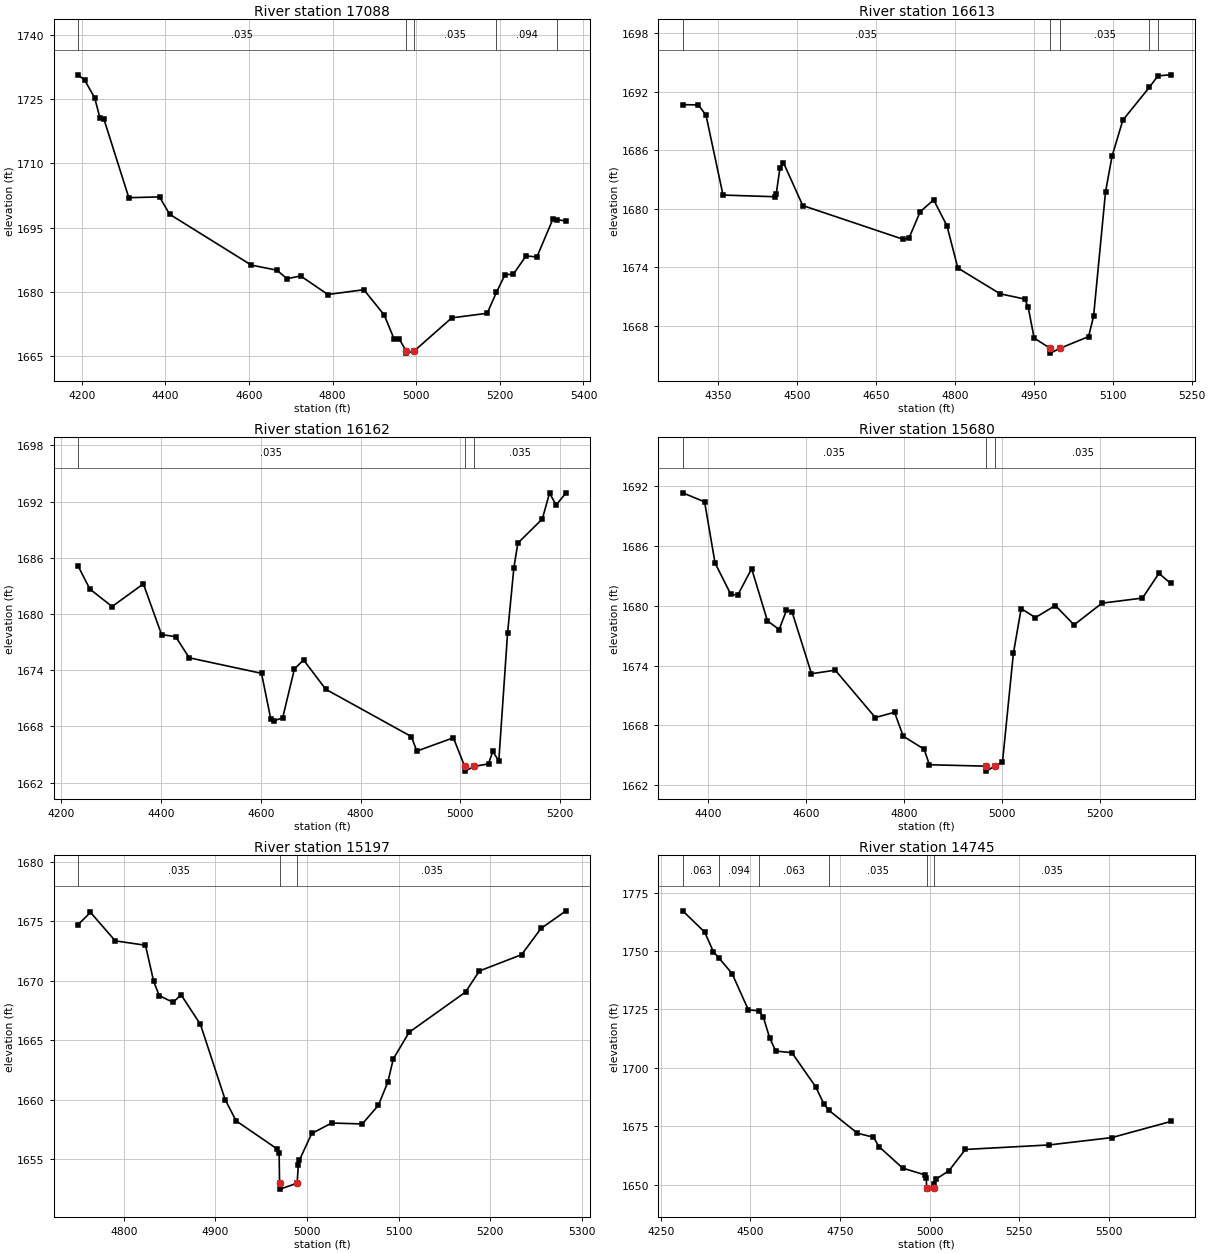
Type RM Length L Ch R = 1 ,17088   ,475,475,475
BEGIN DESCRIPTION:
Quinlan Creek 27.0
END DESCRIPTION:
XS GIS Cut Line= 3
      1931474.99     13932775.01        1930875.       13933325.
      1930624.99     13933575.01
#Sta/Elev= 30
  4190.7 1730.68  4206.6 1729.47  4230.8 1725.29  4243.2 1720.63    4253 1720.28
  4312.4 1701.99  4385.9 1702.17    4410 1698.12  4605.4 1686.25  4666.4 1685.06
  4690.9 1683.07  4723.4 1683.71  4788.5 1679.38  4874.6  1680.5  4923.4 1674.59
  4947.2 1668.93  4958.9 1669.03    4976 1666.19  4976.5 1665.69  4995.1 1666.19
  5084.8 1673.92  5169.7    1675  5191.8 1679.89  5212.1 1683.97  5232.5 1684.16
  5262.6  1688.4  5288.5 1688.14  5326.6 1696.93  5335.8 1696.86  5358.2 1696.55
#Mann= 5 ,-1 , 0
  4190.7    .035       0    4976    .035       0  4995.1    .035       0
  5191.8    .094       0  5335.8     .12       0
Bank Sta=4976,4995.1
XS Rating Curve= 0 ,0
Exp/Cntr=0.3,0.1

Type RM Length L Ch R = 1 ,16613   ,451,451,451
BEGIN DESCRIPTION:
Quinlan Creek 26.0
END DESCRIPTION:
XS GIS Cut Line= 3
      1931125.04     13932674.97        1930525.       13933075.
      1930325.01       13933025.
#Sta/Elev= 30
  4282.9 1690.66  4312.6 1690.63  4327.1 1689.59  4359.5 1681.41  4457.3 1681.24
  4460.5 1681.51  4467.7 1684.18  4474.2 1684.74  4510.9 1680.34    4702 1676.88
  4712.8 1677.01  4734.2 1679.71  4759.7 1680.92    4785 1678.26  4805.6 1673.95
  4885.9 1671.31  4932.8 1670.77  4939.3 1669.94  4950.6 1666.78  4980.9 1665.74
  4981.4 1665.24    5000 1665.74    5054 1666.93  5063.5    1669  5086.2 1681.72
  5098.6 1685.38  5119.2 1689.08  5169.6 1692.44  5185.9 1693.61  5210.2 1693.71
#Mann= 5 ,-1 , 0
  4282.9    .035       0  4980.9    .035       0    5000    .035       0
  5169.6     .12       0  5185.9    .035       0
Bank Sta=4980.9,5000
XS Rating Curve= 0 ,0
Exp/Cntr=0.3,0.1

Type RM Length L Ch R = 1 ,16162   ,482,482,482
BEGIN DESCRIPTION:
Quinlan Creek 25.0
END DESCRIPTION:
XS GIS Cut Line= 3
       1931002.8      13932234.8        1930375.       13932675.
      1930224.99     13932825.01
#Sta/Elev= 30
  4233.1 1685.15  4256.9 1682.66  4301.6 1680.79  4364.3 1683.21  4400.8  1677.8
  4429.1 1677.57  4456.2 1675.32  4601.3 1673.66  4619.7 1668.82  4625.5  1668.6
  4643.6 1668.89  4667.3 1674.13  4685.6 1675.09  4730.1 1671.96  4901.8 1666.91
  4912.8 1665.36  4986.1 1666.78  5008.8 1663.72  5009.3 1663.22  5027.9 1663.72
  5056.6    1664  5065.1 1665.34  5077.2  1664.3  5094.8 1677.96  5107.5 1684.95
  5115.4 1687.56  5164.5 1690.14    5179 1692.91  5192.1 1691.62    5212 1692.93
#Mann= 3 ,-1 , 0
  4233.1    .035       0  5008.8    .035       0  5027.9    .035       0
Bank Sta=5008.8,5027.9
XS Rating Curve= 0 ,0
Exp/Cntr=0.3,0.1

Type RM Length L Ch R = 1 ,15680   ,483,483,483
BEGIN DESCRIPTION:
Quinlan Creek 24.0
END DESCRIPTION:
XS GIS Cut Line= 3
      1930924.97     13931875.02        1930375.       13932225.
      1930049.73     13932337.29
#Sta/Elev= 30
    4348 1691.35  4392.7 1690.44    4414  1684.3    4446 1681.17  4460.2 1681.07
  4488.7 1683.73  4520.9 1678.49  4544.8 1677.62  4559.8 1679.56  4570.9 1679.43
  4610.8 1673.18  4659.3 1673.54  4741.1 1668.78  4780.3 1669.31    4798 1666.91
  4840.7  1665.6  4851.4 1664.04  4966.2  1663.9  4966.7  1663.4  4985.4  1663.9
  5000.6 1664.32  5022.8 1675.22  5038.7 1679.73  5067.6 1678.82  5108.5 1680.03
  5146.6 1678.09  5203.7 1680.27  5286.3 1680.78  5319.8 1683.26    5344 1682.25
#Mann= 3 ,-1 , 0
    4348    .035       0  4966.2    .035       0  4985.4    .035       0
Bank Sta=4966.2,4985.4
XS Rating Curve= 0 ,0
Exp/Cntr=0.3,0.1

Type RM Length L Ch R = 1 ,15197   ,452,452,452
BEGIN DESCRIPTION:
Quinlan Creek 23.0
END DESCRIPTION:
XS GIS Cut Line= 3
        1930625.       13931775.        1930375.       13931775.
      1930175.03     13931974.97
#Sta/Elev= 30
    4750 1674.69  4763.7 1675.73  4790.7 1673.34  4823.7 1672.97  4832.7 1669.93
  4838.7 1668.75  4853.7 1668.18  4862.7  1668.8  4883.7 1666.33  4910.7 1660.01
  4922.7 1658.23  4967.7 1655.86  4969.6 1655.53  4970.1    1653  4970.6  1652.5
  4989.3    1653  4990.6 1654.56  4991.7 1654.92  5005.2 1657.17    5027 1658.05
  5060.4 1657.97  5077.9 1659.53  5088.2 1661.46  5094.3 1663.44  5111.6 1665.67
  5173.1 1669.04  5188.2 1670.81  5234.3 1672.18  5255.5 1674.38  5282.8 1675.86
#Mann= 3 ,-1 , 0
    4750    .035       0  4970.1    .035       0  4989.3    .035       0
Bank Sta=4970.1,4989.3
XS Rating Curve= 0 ,0
Exp/Cntr=0.3,0.1

Type RM Length L Ch R = 1 ,14745   ,412,412,412
BEGIN DESCRIPTION:
Quinlan Creek 22.0
END DESCRIPTION:
XS GIS Cut Line= 3
      1930575.01     13930774.98        1930225.       13931375.
      1929875.49     13931943.16
#Sta/Elev= 30
  4311.4  1767.2  4372.9 1758.05  4397.2  1749.6  4412.5 1747.03  4449.3  1740.3
  4494.5 1724.82  4524.2  1724.4  4536.1 1721.84    4554 1712.81  4570.9 1707.19
    4616 1706.48    4682 1691.98  4705.4 1684.52  4718.8 1681.87    4799    1672
  4843.6 1670.32  4859.1 1666.26  4925.1 1657.08  4987.6 1654.17  4991.1 1653.02
  4991.7 1648.59  4992.2 1648.09  5011.2 1648.59    5012 1650.36  5018.8 1652.41
  5054.3    1656  5100.1 1665.07  5333.7    1667  5508.7 1670.15  5673.1 1677.04
#Mann= 6 ,-1 , 0
  4311.4    .063       0  4412.5    .094       0  4524.2    .063       0
  4718.8    .035       0  4991.7    .035       0  5011.2    .035       0
Bank Sta=4991.7,5011.2
XS Rating Curve= 0 ,0
Exp/Cntr=0.3,0.1

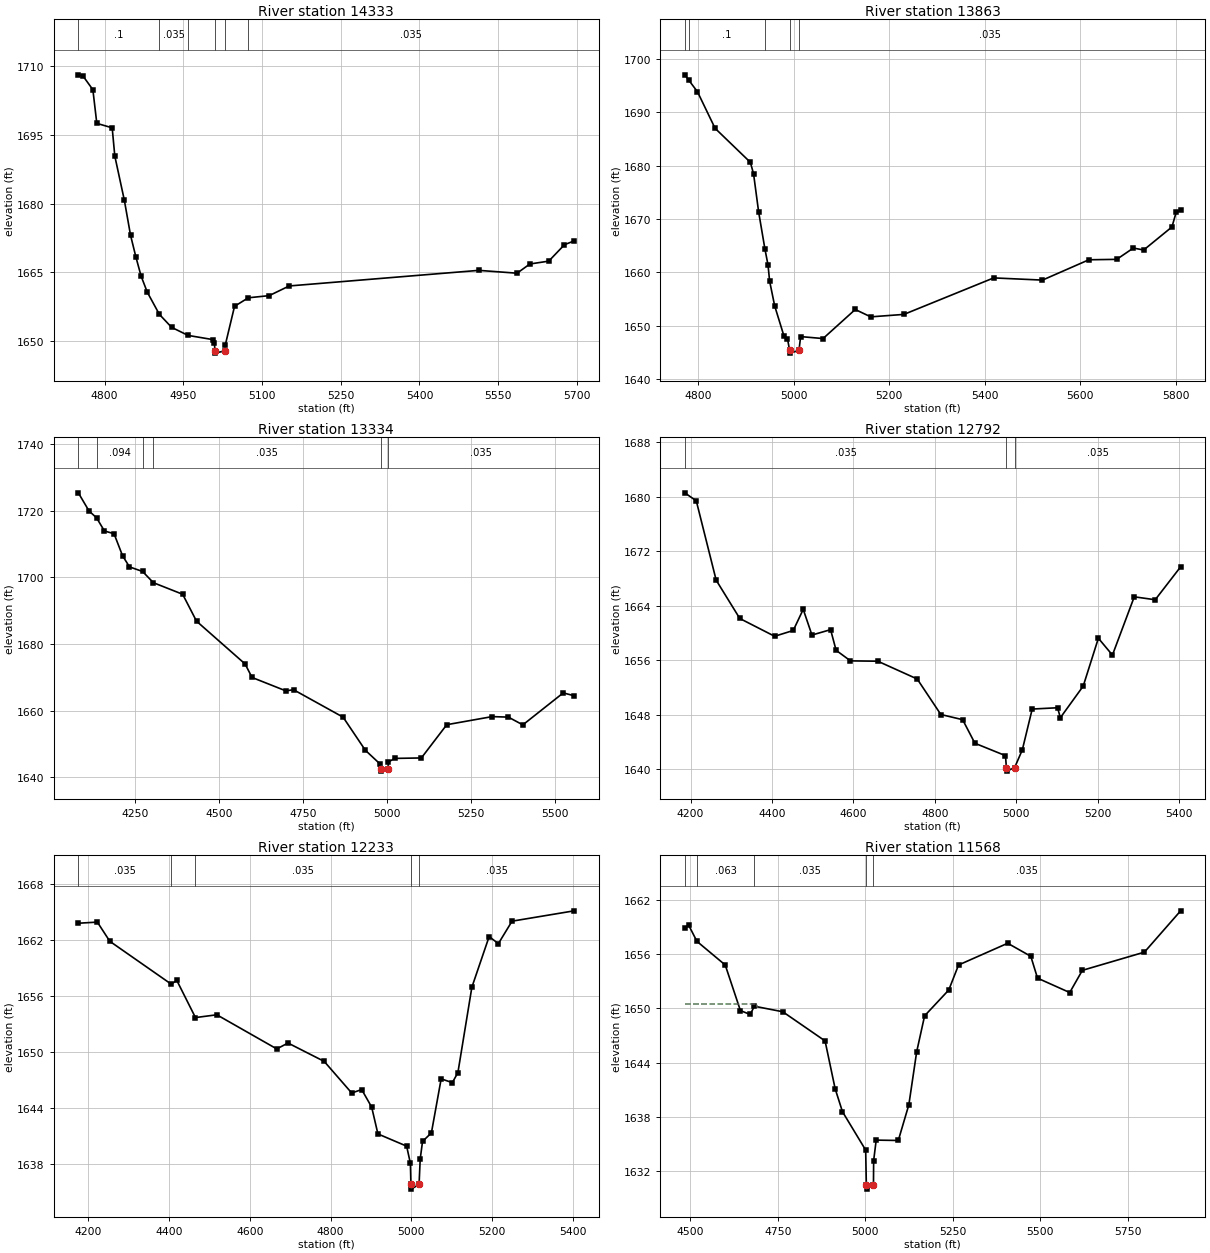
Type RM Length L Ch R = 1 ,14333   ,470,470,470
BEGIN DESCRIPTION:
Quinlan Creek 21.0
END DESCRIPTION:
XS GIS Cut Line= 3
      1930125.02     13930874.97        1929975.       13931075.
      1929624.98     13931675.04
#Sta/Elev= 30
    4750 1708.06  4758.9  1707.8  4777.7 1704.82  4785.2 1697.48  4814.5 1696.51
  4819.5 1690.35  4837.7  1680.7  4849.5 1673.08  4859.5 1668.43  4869.5 1664.22
  4881.3  1660.7  4904.4 1655.85  4927.7 1653.02  4959.2 1651.26  5005.7 1650.36
  5009.4 1649.59  5010.1  1647.9  5010.6  1647.4  5029.6  1647.9  5030.2 1649.27
  5047.6  1657.6  5073.8 1659.46  5113.6 1659.93  5151.8 1662.04    5513 1665.44
  5585.9 1664.82  5610.3 1666.83  5646.3 1667.45  5676.2 1671.03  5694.7 1671.86
#Mann= 6 ,-1 , 0
    4750      .1       0  4904.4    .035       0  4959.2      .1       0
  5010.1     .05       0  5029.6      .1       0  5073.8    .035       0
Bank Sta=5010.1,5029.6
XS Rating Curve= 0 ,0
Exp/Cntr=0.3,0.1

Type RM Length L Ch R = 1 ,13863   ,529,529,529
BEGIN DESCRIPTION:
Quinlan Creek 20.0
END DESCRIPTION:
XS GIS Cut Line= 3
      1929825.02     13930674.99        1929625.       13930775.
      1929074.98     13931375.02
#Sta/Elev= 30
  4772.1 1697.05  4779.9 1696.11  4798.6 1693.88  4835.5 1687.02  4909.3 1680.65
    4916 1678.49  4926.6 1671.36  4939.8 1664.38  4946.2 1661.43  4949.6 1658.38
  4960.2 1653.73  4979.7 1648.06    4987 1647.57  4991.5 1645.38    4992 1644.88
    5011 1645.38  5014.5 1647.98  5061.4 1647.61  5128.8 1653.06  5161.2 1651.68
  5230.6 1652.14  5418.5 1658.98  5520.6 1658.57  5617.7 1662.38    5676 1662.46
  5710.8 1664.58  5732.4 1664.21  5791.5 1668.53  5800.3 1671.25  5809.7 1671.66
#Mann= 5 ,-1 , 0
  4772.1    .063       0  4779.9      .1       0  4939.8    .035       0
  4991.5    .035       0    5011    .035       0
Bank Sta=4991.5,5011
XS Rating Curve= 0 ,0
Exp/Cntr=0.3,0.1

Type RM Length L Ch R = 1 ,13334   ,542,542,542
BEGIN DESCRIPTION:
Quinlan Creek 19.0
END DESCRIPTION:
XS GIS Cut Line= 3
        1929925.       13930225.        1929125.       13930675.
       1928758.8     13931096.44
#Sta/Elev= 30
  4081.7 1725.42  4113.5 1719.98    4136 1717.91  4159.4 1713.96    4188 1713.15
  4213.3 1706.54    4234 1703.18    4273  1701.8  4305.2 1698.43  4392.3 1694.96
  4433.6 1686.88  4578.2 1674.03  4598.8 1669.98  4699.1 1665.97  4722.7 1666.28
    4870 1658.05  4936.1 1648.13  4981.1 1643.89  4983.6 1642.35  4984.1 1641.85
  5003.7 1642.35  5005.1 1644.61  5023.6 1645.67    5103 1645.81  5178.6 1655.79
  5313.6 1658.22    5362 1658.07  5405.1 1655.74  5525.4 1665.34  5557.9 1664.49
#Mann= 6 ,-1 , 0
  4081.7    .063       0    4136    .094       0    4273    .063       0
  4305.2    .035       0  4983.6    .035       0  5003.7    .035       0
Bank Sta=4983.6,5003.7
XS Rating Curve= 0 ,0
Exp/Cntr=0.3,0.1

Type RM Length L Ch R = 1 ,12792   ,559,559,559
BEGIN DESCRIPTION:
Quinlan Creek 18.0
END DESCRIPTION:
XS GIS Cut Line= 3
      1929475.02       13930275.        1928675.       13930425.
      1928324.98     13930625.01
#Sta/Elev= 30
    4186 1680.57  4214.2 1679.39    4263 1667.75    4321 1662.13  4406.5 1659.52
  4452.2 1660.37  4476.7 1663.47  4498.1  1659.7  4543.9 1660.49  4557.4 1657.46
  4592.7 1655.91  4659.8 1655.86  4756.5 1653.25  4814.5 1648.04    4868 1647.28
  4898.1 1643.82  4973.2    1642  4975.4 1640.23  4975.9 1639.73  4995.5 1640.23
  5014.5 1642.85  5038.8 1648.84    5101 1649.03  5107.9 1647.57    5164 1652.21
  5201.2 1659.23  5235.7 1656.76  5289.3 1665.31  5340.7 1664.88  5403.1 1669.71
#Mann= 3 ,-1 , 0
    4186    .035       0  4975.4    .035       0  4995.5    .035       0
Bank Sta=4975.4,4995.5
XS Rating Curve= 0 ,0
Exp/Cntr=0.3,0.1

Type RM Length L Ch R = 1 ,12233   ,665,665,665
BEGIN DESCRIPTION:
Quinlan Creek 17.0
END DESCRIPTION:
XS GIS Cut Line= 3
      1929174.96     13929775.01        1928375.       13929975.
      1928174.99     13930325.01
#Sta/Elev= 30
  4175.4 1663.83  4222.5 1663.95  4253.4 1661.89  4405.3  1657.3  4419.3 1657.69
  4465.4 1653.71  4518.3 1654.01  4666.7 1650.35  4694.6 1650.98  4784.2 1649.01
  4852.3 1645.62    4877 1645.99  4901.7 1644.11  4917.2 1641.23  4988.3 1639.92
  4997.6 1638.08  4998.9 1635.81  4999.4 1635.31  5019.1 1635.81  5021.9 1638.54
  5027.7 1640.43  5049.6 1641.34  5073.8 1647.14  5101.4 1646.73  5115.2  1647.8
  5149.8 1656.96  5192.6  1662.4  5215.4 1661.64  5249.3 1664.05  5403.1 1665.16
#Mann= 5 ,-1 , 0
  4175.4    .035       0  4405.3    .063       0  4465.4    .035       0
  4998.9    .035       0  5019.1    .035       0
Bank Sta=4998.9,5019.1
XS Rating Curve= 0 ,0
Exp/Cntr=0.3,0.1

Type RM Length L Ch R = 1 ,11568   ,464,464,464
BEGIN DESCRIPTION:
Quinlan Creek 16.0
END DESCRIPTION:
XS GIS Cut Line= 3
      1928975.02     13929625.01      1928530.73     13929507.08
      1927575.02       13929575.
#Sta/Elev= 30
  4483.9 1658.89    4495 1659.17  4518.6 1657.39  4599.5 1654.78  4642.9 1649.75
  4670.9 1649.32  4682.8 1650.23    4764 1649.62    4885  1646.4  4913.7 1641.14
  4934.7 1638.59  5001.1 1634.35    5003 1630.54  5003.5 1630.04  5023.4 1630.54
  5023.9 1633.19  5031.2 1635.45  5094.4 1635.41  5124.6 1639.36  5146.9 1645.19
  5169.6 1649.17  5238.7 1652.02  5266.7 1654.78  5407.2 1657.18  5473.3 1655.74
  5492.5 1653.33  5584.6 1651.74  5620.7 1654.19  5798.2  1656.2  5901.7 1660.76
#Mann= 5 ,-1 , 0
  4483.9    .035       0  4518.6    .063       0  4682.8    .035       0
    5003    .035       0  5023.4    .035       0
#XS Ineff= 2 , 0
         4689.31 1650.47
Permanent Ineff=
       F       F
Bank Sta=5003,5023.4
XS Rating Curve= 0 ,0
Exp/Cntr=0.3,0.1