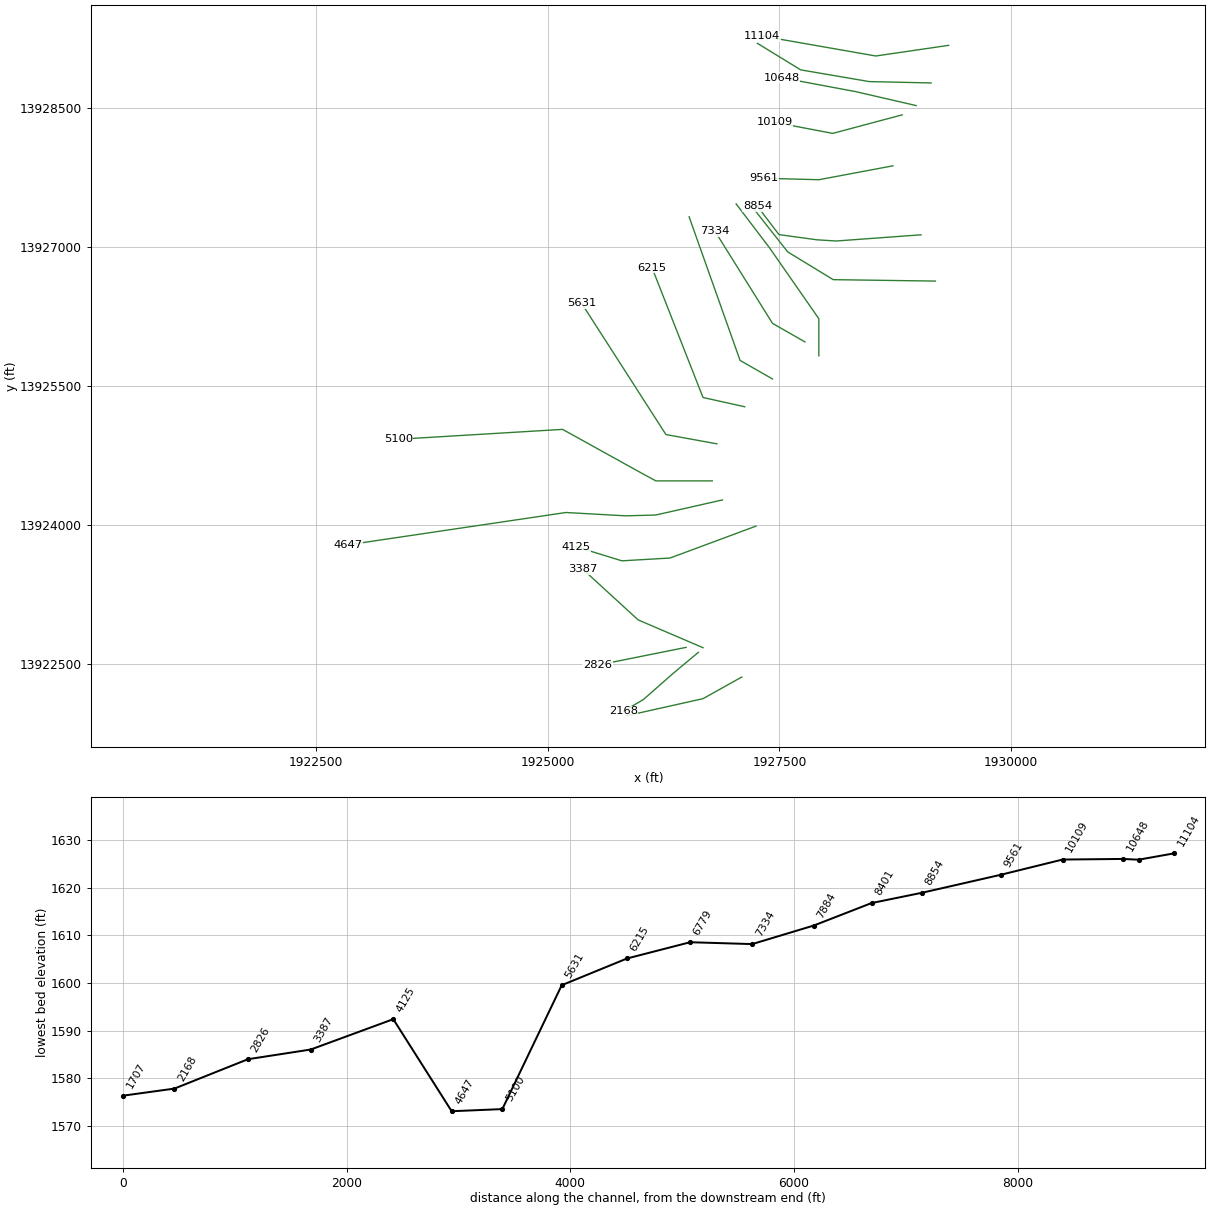
HEC-RAS study Quinlan Creek.prj: Quinlan Creek Base Level Engineering

--- Quinlan Creek.g01 (geometry) --- (continued)

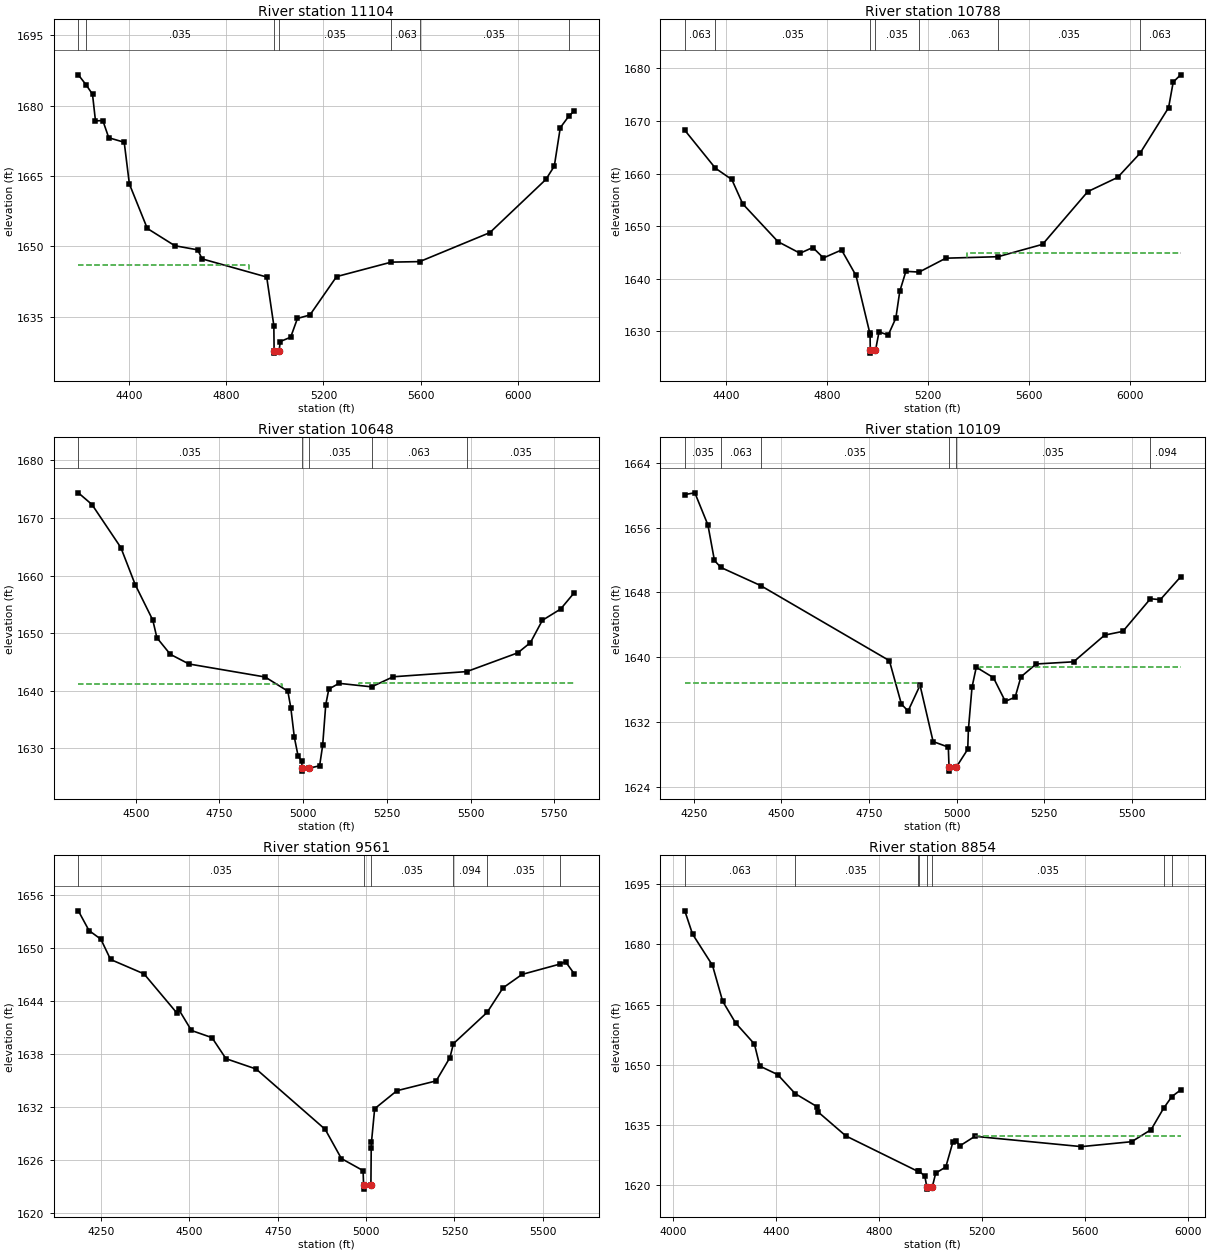
Type RM Length L Ch R = 1 ,11104   ,316,316,316
BEGIN DESCRIPTION:
Quinlan Creek 15.0
END DESCRIPTION:
XS GIS Cut Line= 3
      1929325.03       13929175.      1928539.69      13929060.1
      1927312.86     13929274.92
#Sta/Elev= 30
  4192.1 1686.58    4225 1684.38  4250.4 1682.43  4262.6 1676.75  4292.9 1676.82
  4317.2 1673.15  4380.8 1672.19    4402 1663.29  4475.7  1653.8    4589 1650.11
    4683 1649.23  4701.2  1647.3  4966.8 1643.43  4996.2 1633.06  4997.3 1627.69
  4997.8 1627.19  5017.8 1627.69  5022.7 1629.67  5065.4 1630.59  5093.2 1634.59
  5144.6 1635.33  5254.2 1643.52  5479.2 1646.61  5596.1 1646.72  5884.7 1652.91
  6114.9 1664.25  6149.6 1667.09  6174.2 1675.29  6208.7 1677.72  6231.3 1678.87
#Mann= 7 ,-1 , 0
  4192.1    .063       0    4225    .035       0  4997.3    .035       0
  5017.8    .035       0  5479.2    .063       0  5596.1    .035       0
  6208.7    .063       0
#XS Ineff= 2 , 0
         4894.11 1645.99
Permanent Ineff=
       F       F
Bank Sta=4997.3,5017.8
XS Rating Curve= 0 ,0
Exp/Cntr=0.3,0.1

Type RM Length L Ch R = 1 ,10788   ,140,140,140
BEGIN DESCRIPTION:
Mapping XS e5fe7a68
END DESCRIPTION:
XS GIS Cut Line= 4
      1929136.69     13928769.12      1928468.22     13928784.06
      1927728.96     13928910.49      1927262.59     13929196.46
#Sta/Elev= 30
  4236.7 1668.24  4358.2 1661.02  4423.1 1658.88  4466.3 1654.25  4606.2 1647.06
  4693.5 1644.86  4744.2 1645.95  4786.2 1643.97  4858.2 1645.48  4915.4 1640.63
  4970.2 1629.67  4971.3 1629.23    4972 1626.37  4972.5 1625.87  4992.6 1626.37
  5006.7 1629.91  5043.2 1629.31  5073.4 1632.53  5088.9  1637.6  5113.2 1641.42
  5165.8 1641.28  5271.5 1643.92  5478.3  1644.2    5655 1646.55  5834.4 1656.58
  5952.8 1659.28  6041.2 1663.85  6154.6 1672.53    6173  1677.4  6202.4 1678.78
#Mann= 7 ,-1 , 0
  4236.7    .063       0  4358.2    .035       0    4972    .035       0
  4992.6    .035       0  5165.8    .063       0  5478.3    .035       0
  6041.2    .063       0
#XS Ineff= 2 , 0
         4854.15 1645.39 5353.65         1644.91
Permanent Ineff=
       F       F
Bank Sta=4972,4992.6
XS Rating Curve= 0 ,0
Exp/Cntr=0.3,0.1

Type RM Length L Ch R = 1 ,10648   ,539,539,539
BEGIN DESCRIPTION:
Quinlan Creek 14.0
END DESCRIPTION:
XS GIS Cut Line= 3
      1928974.99       13928525.        1928325.       13928675.
      1927525.01       13928825.
#Sta/Elev= 30
  4328.5 1674.37  4369.2 1672.34  4455.4 1664.87  4498.5 1658.41  4550.9 1652.26
  4563.2 1649.19  4603.2 1646.32  4658.9 1644.64  4886.5 1642.38  4954.2 1639.92
  4963.1 1637.07  4973.7 1631.91    4985 1628.63  4996.2 1627.72  4996.5 1626.53
    4997 1626.03  5017.2 1626.53  5049.2 1626.96  5058.3  1630.5  5067.5 1637.56
  5076.7 1640.28  5107.2 1641.28  5204.5 1640.67    5269 1642.42  5488.8 1643.32
  5641.3 1646.58  5678.8 1648.35  5714.6 1652.23    5769 1654.18  5809.5    1657
#Mann= 5 ,-1 , 0
  4328.5    .035       0  4996.5    .035       0  5017.2    .035       0
  5204.5    .063       0  5488.8    .035       0
#XS Ineff= 2 , 0
         4935.46  1641.2 5165.63         1641.32
Permanent Ineff=
       F       F
Bank Sta=4996.5,5017.2
XS Rating Curve= 0 ,0
Exp/Cntr=0.3,0.1

Type RM Length L Ch R = 1 ,10109   ,548,548,548
BEGIN DESCRIPTION:
Quinlan Creek 13.0
END DESCRIPTION:
XS GIS Cut Line= 3
      1928825.03     13928425.01        1928075.       13928225.
      1927447.42     13928344.48
#Sta/Elev= 30
  4224.1 1660.08  4252.8 1660.29  4290.1 1656.32  4308.7 1651.93    4327 1651.07
  4440.5 1648.83    4808 1639.55  4842.3 1634.18  4861.4 1633.33  4895.5 1636.51
  4932.8 1629.55  4976.2 1628.87  4978.2  1626.4  4978.7  1625.9    4999  1626.4
  5031.6  1628.6  5033.5 1631.05  5043.8 1636.27    5056 1638.74  5104.9 1637.45
  5138.7 1634.53  5166.9 1635.03  5183.4 1637.55    5227 1639.14  5333.9 1639.41
  5422.5 1642.71  5474.4 1643.17    5553  1647.2  5581.3 1647.09  5639.2 1649.91
#Mann= 6 ,-1 , 0
  4224.1    .035       0    4327    .063       0  4440.5    .035       0
  4978.2    .035       0    4999    .035       0    5553    .094       0
#XS Ineff= 2 , 0
         4892.11 1636.82 5066.33         1638.73
Permanent Ineff=
       F       F
Bank Sta=4978.2,4999
XS Rating Curve= 0 ,0
Exp/Cntr=0.3,0.1

Type RM Length L Ch R = 1 ,9561    ,707,707,707
BEGIN DESCRIPTION:
Quinlan Creek 12.0
END DESCRIPTION:
XS GIS Cut Line= 3
      1928724.98       13927875.        1927925.       13927725.
      1927335.92     13927740.53
#Sta/Elev= 30
  4185.7  1654.2  4215.9 1651.97  4249.5 1650.99  4276.9  1648.7  4371.6 1647.07
  4464.7 1642.64  4469.8 1643.05  4505.8 1640.67  4563.9 1639.86  4603.5 1637.48
    4689 1636.31  4884.3 1629.49  4930.1 1626.19  4991.6 1624.82  4992.9 1623.23
  4993.4 1622.73  5013.7 1623.23  5014.6 1627.43  5015.3 1628.04  5024.3 1631.82
  5087.3 1633.86  5198.4 1634.97  5237.4 1637.61  5247.2 1639.18  5342.7 1642.72
  5387.6 1645.49  5441.5 1647.01  5548.8 1648.18  5564.5 1648.45  5588.9 1647.09
#Mann= 6 ,-1 , 0
  4185.7    .035       0  4992.9    .035       0  5013.7    .035       0
  5247.2    .094       0  5342.7    .035       0  5548.8    .094       0
Bank Sta=4992.9,5013.7
XS Rating Curve= 0 ,0
Exp/Cntr=0.3,0.1

Type RM Length L Ch R = 1 ,8854    ,453,453,453
BEGIN DESCRIPTION:
Quinlan Creek 11.1
END DESCRIPTION:
XS GIS Cut Line= 5
       1929027.8     13927130.59      1928112.65     13927063.71
      1927904.52     13927076.56      1927494.98     13927132.71
       1927261.6     13927439.17
#Sta/Elev= 30
  4044.9  1688.4  4074.8 1682.61  4152.4 1674.79  4191.8 1665.84  4242.1 1660.41
  4315.1 1655.16  4336.2 1649.64  4405.4 1647.53  4473.1 1642.79  4558.8  1639.5
  4561.8 1638.23  4670.1 1632.22  4948.2 1623.42  4955.4 1623.43  4976.9  1622.1
  4984.5 1619.44    4985 1618.94  5005.4 1619.44    5019 1622.95    5058 1624.46
  5085.1 1630.58  5097.1 1630.98    5113 1629.75    5171 1632.12  5584.4 1629.55
  5779.7 1630.78  5855.1 1633.79  5903.2 1639.09  5935.5 1642.03  5969.6 1643.69
#Mann= 8 ,-1 , 0
  4044.9    .063       0  4473.1    .035       0  4948.2    .063       0
  4955.4    .035       0  4984.5    .035       0  5005.4    .035       0
  5903.2    .063       0  5935.5    .035       0
#XS Ineff= 2 , 0
                         5173.02         1632.13
Permanent Ineff=
       F       F
Bank Sta=4984.5,5005.4
XS Rating Curve= 0 ,0
Exp/Cntr=0.3,0.1

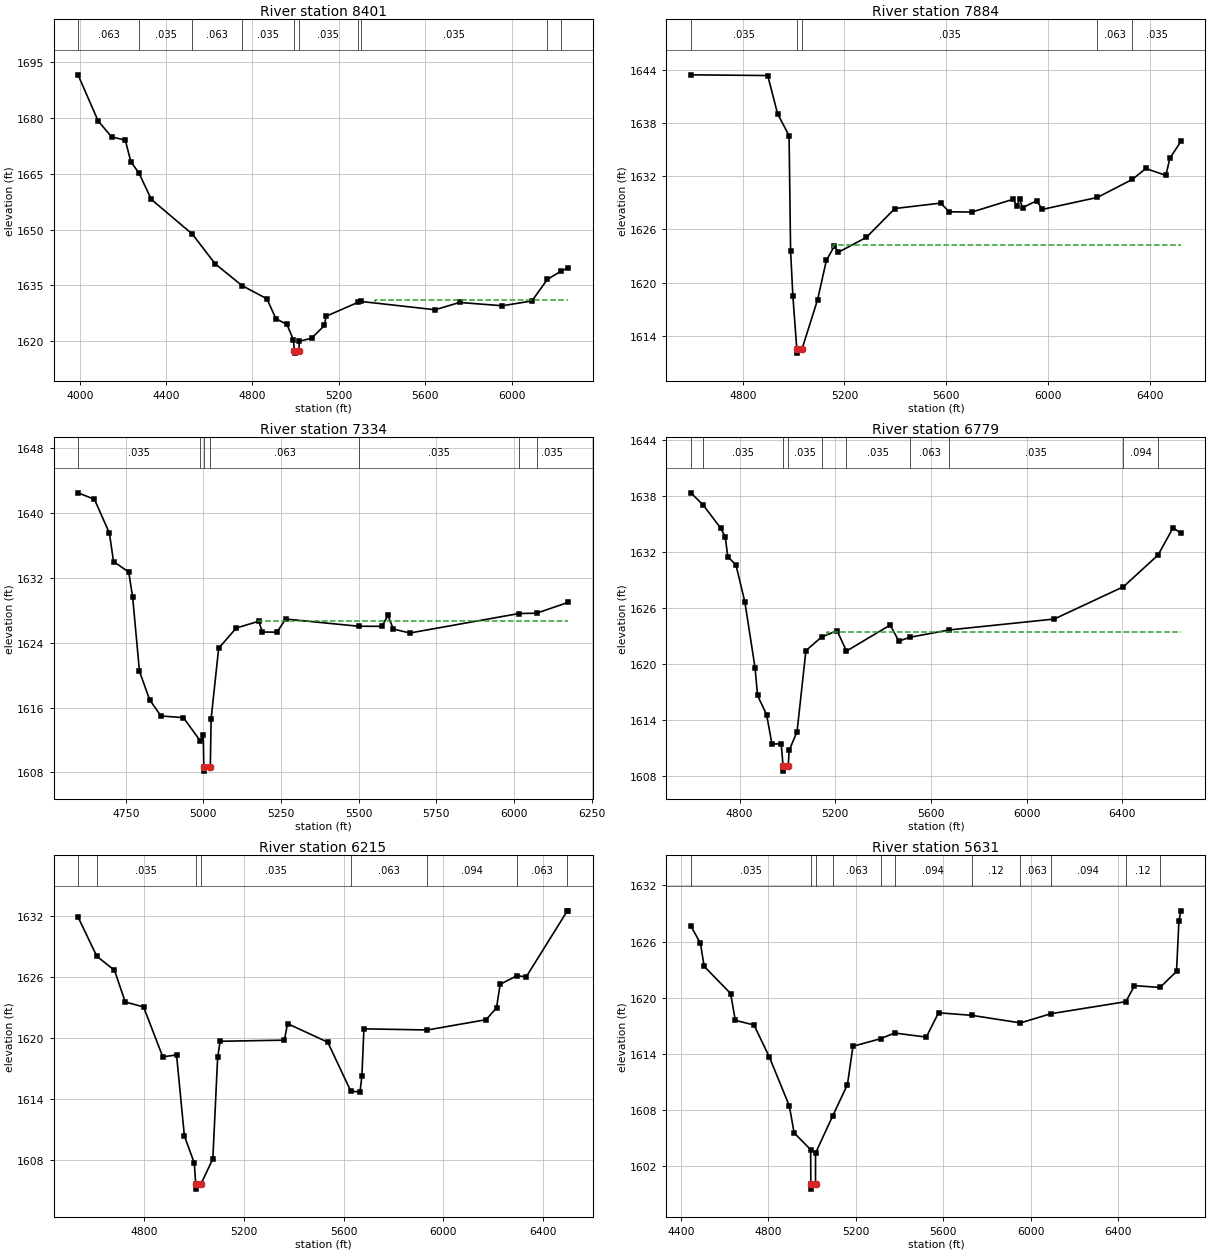
Type RM Length L Ch R = 1 ,8401    ,517,517,517
BEGIN DESCRIPTION:
Mapping XS 2b4b20cd
END DESCRIPTION:
XS GIS Cut Line= 4
       1929182.8     13926631.19      1928079.94     13926646.61
      1927589.52     13926945.91      1927222.75     13927410.35
#Sta/Elev= 30
  3992.3 1691.65  4084.8 1679.31  4147.8 1674.93    4211  1674.1  4236.8 1668.28
  4274.3 1665.22  4331.7 1658.13  4521.9 1648.78  4626.9 1640.83  4751.3 1634.96
  4866.9 1631.39  4908.9 1626.02  4959.9 1624.48  4989.9  1620.3  4994.5 1617.27
    4995 1616.77  5015.4 1617.27  5016.9 1619.95  5073.9  1620.8  5133.5 1624.21
  5140.5 1626.67  5287.9 1630.41  5301.3 1630.68    5646 1628.44  5758.9  1630.4
  5957.4 1629.52  6094.3 1630.81  6165.8 1636.61  6227.3 1638.74  6261.6 1639.71
#Mann= 10 ,-1 , 0
  3992.3    .063       0  4274.3    .035       0  4521.9    .063       0
  4751.3    .035       0  4994.5    .035       0  5015.4    .035       0
  5287.9    .063       0  5301.3    .035       0  6165.8    .063       0
  6227.3    .035       0
#XS Ineff= 2 , 0
                         5368.52          1631.1
Permanent Ineff=
       F       F
Bank Sta=4994.5,5015.4
XS Rating Curve= 0 ,0
Exp/Cntr=0.3,0.1

Type RM Length L Ch R = 1 ,7884    ,550,550,550
BEGIN DESCRIPTION:
Quinlan Creek 11.0
END DESCRIPTION:
XS GIS Cut Line= 4
        1927925.     13925824.98        1927925.       13926225.
      1927391.64     13926991.76      1927032.62     13927464.05
#Sta/Elev= 30
    4596  1643.4  4898.1 1643.32  4937.1    1639  4982.1 1636.55  4988.1 1623.52
  4997.2 1618.43  5012.4 1612.55  5012.9 1612.05  5033.4 1612.55  5094.3 1618.07
  5128.9 1622.51  5160.1 1624.09  5176.4 1623.42  5286.2 1625.09  5398.2 1628.34
  5578.4 1628.95  5611.9 1627.97  5701.2 1627.94  5863.4 1629.38    5878 1628.61
    5889 1629.41  5900.3 1628.44  5956.2 1629.21  5978.2 1628.24    6195 1629.59
  6332.2 1631.62  6385.2 1632.85  6464.3 1632.07  6479.4 1633.98  6523.3 1635.91
#Mann= 5 ,-1 , 0
    4596    .035       0  5012.4    .035       0  5033.4    .035       0
    6195    .063       0  6332.2    .035       0
#XS Ineff= 2 , 0
                         5156.84         1624.25
Permanent Ineff=
       F       F
Bank Sta=5012.4,5033.4
XS Rating Curve= 0 ,0
Exp/Cntr=0.3,0.1

Type RM Length L Ch R = 1 ,7334    ,555,555,555
BEGIN DESCRIPTION:
Quinlan Creek 10.0
END DESCRIPTION:
XS GIS Cut Line= 3
      1927775.02     13925974.99        1927425.       13926175.
      1926802.95     13927170.97
#Sta/Elev= 30
  4596.6 1642.47  4649.4 1641.67  4697.5 1637.51  4710.8    1634  4759.8  1632.7
  4772.4 1629.61  4794.3 1620.47  4827.3 1616.94  4863.5 1614.96    4936 1614.75
  4990.4 1611.87  4999.7 1612.57  5001.4 1608.66  5001.9 1608.16  5022.4 1608.66
    5025 1614.62  5049.3 1623.31  5105.9  1625.8  5178.5 1626.64  5189.8 1625.31
  5236.8 1625.29  5265.1 1626.91  5499.7 1626.02  5574.9 1626.01    5594 1627.35
  5611.7 1625.67  5664.8 1625.19    6016 1627.59  6072.6 1627.63    6174 1628.96
#Mann= 7 ,-1 , 0
  4596.6    .035       0  4990.4    .063       0  5001.4     .05       0
  5022.4    .063       0  5499.7    .035       0    6016    .094       0
  6072.6    .035       0
#XS Ineff= 2 , 0
                         5175.02         1626.64
Permanent Ineff=
       F       F
Bank Sta=5001.4,5022.4
XS Rating Curve= 0 ,0
Exp/Cntr=0.3,0.1

Type RM Length L Ch R = 1 ,6779    ,564,564,564
BEGIN DESCRIPTION:
Quinlan Creek 9.0
END DESCRIPTION:
XS GIS Cut Line= 3
      1927424.98     13925575.01        1927075.       13925775.
      1926524.99     13927325.02
#Sta/Elev= 30
  4596.9 1638.34    4649 1637.01  4721.3 1634.56  4740.5 1633.62  4750.9 1631.52
  4785.4  1630.6  4822.4 1626.65  4864.9 1619.63  4875.4 1616.65  4913.3 1614.59
  4935.6 1611.44  4974.2 1611.48  4982.2 1609.05  4982.7 1608.55  5003.3 1609.05
  5007.6 1610.77  5040.5 1612.77  5077.5 1621.45  5143.7 1622.92    5208 1623.57
    5247  1621.4  5429.7 1624.19  5465.8 1622.47  5512.6 1622.88  5675.2 1623.66
  6115.3 1624.83  6404.6 1628.29  6549.4 1631.69  6611.9  1634.6  6644.7    1634
#Mann= 10 ,-1 , 0
  4596.9    .063       0    4649    .035       0  4982.2    .035       0
  5003.3    .035       0  5143.7    .063       0    5247    .035       0
  5512.6    .063       0  5675.2    .035       0  6404.6    .094       0
  6549.4     .12       0
#XS Ineff= 2 , 0
                         5166.83         1623.44
Permanent Ineff=
       F       F
Bank Sta=4982.2,5003.3
XS Rating Curve= 0 ,0
Exp/Cntr=0.3,0.1

Type RM Length L Ch R = 1 ,6215    ,584,584,584
BEGIN DESCRIPTION:
Quinlan Creek 8.0
END DESCRIPTION:
XS GIS Cut Line= 3
      1927125.01       13925275.        1926675.       13925375.
      1926124.98     13926775.04
#Sta/Elev= 30
  4534.7 1631.86  4609.9 1628.01  4680.9 1626.63  4723.9 1623.52  4797.6 1623.03
  4874.5 1618.13  4929.8 1618.32  4961.1 1610.38  5001.1 1607.68  5006.6 1605.64
  5007.1 1605.14  5027.7 1605.64  5075.3 1608.12  5094.6 1618.07  5104.3 1619.66
  5362.1 1619.77    5375 1621.39  5536.2 1619.57  5628.3 1614.77  5665.3 1614.67
  5673.1 1616.22  5681.2 1620.88  5936.2 1620.77  6171.2 1621.78  6213.1 1622.95
  6227.4 1625.25  6294.9  1626.1  6332.3 1625.99  6496.8 1632.46  6499.9 1632.47
#Mann= 8 ,-1 , 0
  4534.7    .094       0  4609.9    .035       0  5006.6    .035       0
  5027.7    .035       0  5628.3    .063       0  5936.2    .094       0
  6294.9    .063       0  6496.8    .094       0
#XS Ineff= 2 , 0
                         5383.12         1620.39
Permanent Ineff=
       F       F
Bank Sta=5006.6,5027.7
XS Rating Curve= 0 ,0
Exp/Cntr=0.3,0.1

Type RM Length L Ch R = 1 ,5631    ,531,531,531
BEGIN DESCRIPTION:
Quinlan Creek 7.0
END DESCRIPTION:
XS GIS Cut Line= 3
      1926824.98       13924875.        1926275.       13924975.
      1925366.44     13926389.66
#Sta/Elev= 30
  4445.7 1627.65  4489.3 1625.81  4506.1 1623.35  4627.3 1620.44  4648.7 1617.57
    4734 1617.08  4804.2 1613.66  4895.6 1608.43  4917.6 1605.54  4993.2 1603.75
    4994 1600.03  4994.5 1599.53  5015.4 1600.03  5015.5 1603.38  5093.8 1607.35
  5161.4 1610.71  5186.6  1614.8  5312.9 1615.61  5376.6 1616.22  5521.8 1615.78
  5577.8 1618.38  5728.8 1618.11  5952.5  1617.3  6091.4 1618.28  6434.2 1619.57
  6473.7 1621.28  6590.7 1621.09  6665.9  1622.8    6677 1628.23    6686 1629.28
#Mann= 11 ,-1 , 0
  4445.7    .035       0    4994    .035       0  5015.4    .035       0
  5093.8    .063       0  5312.9    .035       0  5376.6    .094       0
  5728.8     .12       0  5952.5    .063       0  6091.4    .094       0
  6434.2     .12       0  6590.7    .094       0
Bank Sta=4994,5015.4
XS Rating Curve= 0 ,0
Exp/Cntr=0.3,0.1

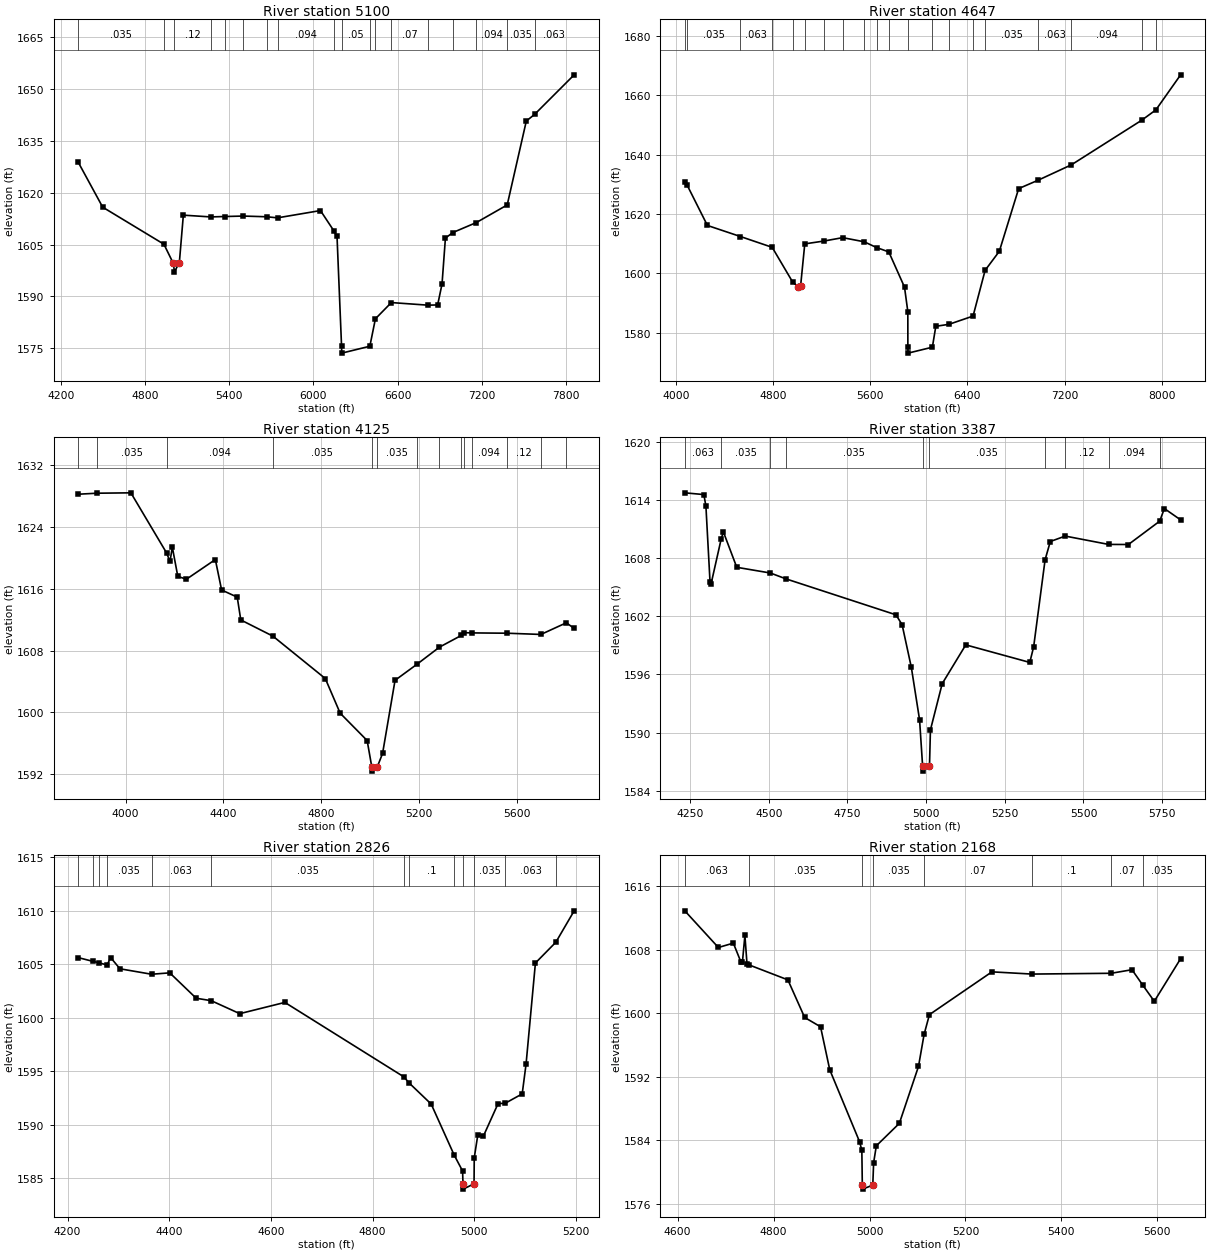
Type RM Length L Ch R = 1 ,5100    ,453,453,453
BEGIN DESCRIPTION:
Quinlan Creek 6.0
END DESCRIPTION:
XS GIS Cut Line= 5
      1926774.99       13924475.      1926166.81       13924475.
      1926036.76     13924545.11      1925159.82     13925031.01
      1923387.21     13924924.29
#Sta/Elev= 30
  4324.3 1628.79    4498 1615.82  4934.3 1605.09  5000.8 1599.58  5009.7 1597.12
  5044.3 1599.75  5072.8 1613.51  5266.7    1613  5367.4 1613.11  5500.4 1613.25
  5666.4 1613.04    5744 1612.73  6050.2 1614.84  6146.2 1608.94  6168.3 1607.33
  6200.6 1575.53  6202.1 1573.53  6402.3 1575.53  6441.9 1583.48  6555.5 1588.18
  6815.1 1587.43  6885.5 1587.49  6916.8 1593.57  6940.9 1606.86  6993.2 1608.46
  7161.7 1611.37  7381.4 1616.47  7517.6 1640.79    7576 1642.68  7858.6 1654.17
#Mann= 18 ,-1 , 0
  4324.3    .035       0  4934.3    .094       0  5009.7     .12       0
  5266.7    .094       0  5367.4    .035       0  5500.4    .094       0
  5666.4     .12       0    5744    .094       0  6146.2      .1       0
  6200.6     .05       0  6402.3      .1       0  6441.9      .1       0
  6555.5     .07       0  6815.1    .035       0  6993.2    .063       0
  7161.7    .094       0  7381.4    .035       0    7576    .063       0
#Block Obstruct= 2 , 0
                         5534.47         1613.29
Bank Sta=5000.8,5044.3
XS Rating Curve= 0 ,0
Exp/Cntr=0.3,0.1

Type RM Length L Ch R = 1 ,4647    ,522,522,522
BEGIN DESCRIPTION:
Quinlan Creek 5.2
END DESCRIPTION:
XS GIS Cut Line= 5
      1926884.79     13924269.61      1926164.34     13924106.58
      1925838.42     13924098.05      1925195.42      13924133.9
      1922845.52     13923785.39
#Sta/Elev= 30
  4071.9 1630.61  4090.2 1629.76    4258  1616.1    4530 1612.37  4791.7 1608.73
  4961.7 1596.94  5006.7 1595.48  5025.8  1595.7  5060.2 1609.89  5217.2 1610.84
  5372.4 1611.99  5549.3  1610.6  5653.4 1608.62  5752.3 1607.19  5881.8 1595.31
  5909.1 1587.05  5909.4 1575.08    5911 1573.08  6111.2 1575.08  6139.6 1582.12
  6248.2 1582.79  6446.5 1585.57  6545.7 1600.98  6662.7 1607.39    6822 1628.51
  6982.1 1631.34    7257 1636.54  7835.2 1651.54  7952.3 1655.03  8156.2 1666.85
#Mann= 20 ,-1 , 0
  4071.9    .063       0  4090.2    .035       0    4530    .063       0
  4791.7    .035       0  4961.7    .094       0  5060.2     .12       0
  5217.2    .094       0  5372.4     .12       0  5549.3    .094       0
  5653.4    .063       0  5752.3     .07       0  5909.4     .05       0
  6111.2     .07       0  6248.2     .07       0  6446.5      .1       0
  6545.7    .035       0  6982.1    .063       0    7257    .094       0
  7835.2     .12       0  7952.3    .094       0
#Block Obstruct= 2 , 0
                         5388.61         1612.22
Bank Sta=5006.7,5025.8
XS Rating Curve= 0 ,0
Exp/Cntr=0.3,0.1

Type RM Length L Ch R = 1 ,4125    ,738,738,738
BEGIN DESCRIPTION:
Quinlan Creek 5.1
END DESCRIPTION:
XS GIS Cut Line= 4
      1927246.87     13923987.03      1926319.19     13923642.66
      1925799.18     13923612.37      1925303.83     13923765.12
#Sta/Elev= 30
  3806.6 1628.26  3882.3 1628.39  4021.6 1628.44  4167.8 1620.65  4181.6 1619.55
  4191.2  1621.4  4213.6 1617.62  4248.8 1617.25  4367.2  1619.8  4392.8 1615.86
  4456.8 1614.93  4471.3 1611.98  4602.8 1609.88  4817.1 1604.39    4878  1599.9
  4988.4 1596.36  5007.6  1592.9  5008.1  1592.4  5029.2  1592.9  5051.5 1594.69
  5102.5 1604.16  5193.5 1606.27  5284.4 1608.46  5373.5 1609.97  5384.3 1610.33
  5416.6  1610.3  5560.7 1610.26  5699.3  1610.1  5803.5 1611.61  5835.4 1610.88
#Mann= 14 ,-1 , 0
  3806.6    .063       0  3882.3    .035       0  4167.8    .094       0
  4602.8    .035       0  5007.6    .035       0  5029.2    .035       0
  5193.5    .094       0  5284.4     .12       0  5373.5    .094       0
  5384.3     .12       0  5416.6    .094       0  5560.7     .12       0
  5699.3    .063       0  5803.5    .035       0
Bank Sta=5007.6,5029.2
XS Rating Curve= 0 ,0
Exp/Cntr=0.3,0.1

Type RM Length L Ch R = 1 ,3387    ,561,561,561
BEGIN DESCRIPTION:
Quinlan Creek 5.0
END DESCRIPTION:
XS GIS Cut Line= 3
      1926675.01       13922675.        1925975.       13922975.
      1925375.02     13923524.98
#Sta/Elev= 30
  4233.2 1614.73  4293.8 1614.55  4300.3 1613.35  4313.4 1605.52  4316.7 1605.34
    4349    1610  4355.8  1610.7  4398.3 1607.05  4505.3 1606.46  4554.3 1605.86
  4904.2 1602.15  4923.7 1601.13  4953.1 1596.72  4979.2 1591.32  4988.9 1586.53
  4989.4 1586.03  5010.7 1586.53  5013.7 1590.28  5051.1 1595.05    5126 1599.05
  5329.4 1597.24  5341.7 1598.85    5378 1607.82  5394.6 1609.71    5442 1610.27
  5579.8 1609.41  5642.8  1609.4  5742.3 1611.81    5757 1613.11  5808.7 1611.94
#Mann= 10 ,-1 , 0
  4233.2    .063       0    4349    .035       0  4505.3    .063       0
  4554.3    .035       0  4988.9    .035       0  5010.7    .035       0
    5378    .094       0    5442     .12       0  5579.8    .094       0
  5742.3     .12       0
Bank Sta=4988.9,5010.7
XS Rating Curve= 0 ,0
Exp/Cntr=0.3,0.1

Type RM Length L Ch R = 1 ,2826    ,658,658,658
BEGIN DESCRIPTION:
Mapping XS 794f0293
END DESCRIPTION:
XS GIS Cut Line= 2
      1926492.55     13922678.58      1925536.42     13922486.66
#Sta/Elev= 30
  4221.3 1605.61  4250.2 1605.26  4261.9 1605.13    4278 1604.92  4284.8 1605.62
  4303.1 1604.57  4365.3 1604.06  4401.1 1604.19  4453.1 1601.82  4482.8 1601.59
  4538.8 1600.38  4627.5 1601.43  4861.6 1594.48  4871.7 1593.92  4915.3 1591.94
  4960.7 1587.16  4977.1 1585.69  4977.8  1584.5  4978.3    1584  4999.6  1584.5
    5000 1586.93  5007.1 1589.09  5017.8 1588.93  5046.9 1591.99  5060.6 1592.01
  5094.3 1592.89  5101.9 1595.67  5120.3 1605.11  5160.5 1607.05  5196.5 1609.98
#Mann= 13 ,-1 , 0
  4221.3    .063       0  4250.2    .035       0  4261.9    .063       0
    4278    .035       0  4365.3    .063       0  4482.8    .035       0
  4861.6     .07       0  4871.7      .1       0  4960.7    .035       0
  4977.8    .035       0  4999.6    .035       0  5060.6    .063       0
  5160.5    .035       0
Bank Sta=4977.8,4999.6
XS Rating Curve= 0 ,0
Exp/Cntr=0.3,0.1

Type RM Length L Ch R = 1 ,2168    ,461,461,461
BEGIN DESCRIPTION:
Quinlan Creek 4.0
END DESCRIPTION:
XS GIS Cut Line= 4
      1926625.03     13922625.03      1926351.29     13922396.63
      1926030.03     13922114.17       1925814.5     13921988.65
#Sta/Elev= 30
  4614.9  1612.9  4684.9 1608.28  4716.1 1608.83  4731.8 1606.47    4735 1606.43
  4740.2  1609.8  4744.6  1606.2  4747.8 1606.11  4829.8  1604.2  4864.8 1599.46
  4897.9 1598.29  4917.1 1592.87  4979.5 1583.77    4984 1582.71    4985 1578.33
  4985.5 1577.83  5006.8 1578.33  5008.6 1581.17  5014.2 1583.29  5062.2 1586.12
  5102.1 1593.29  5113.8 1597.33  5124.9 1599.82  5255.2 1605.21  5338.7 1604.93
  5503.9 1605.03  5547.2 1605.48  5570.1  1603.5  5593.7  1601.5  5648.6 1606.87
#Mann= 8 ,-1 , 0
  4614.9    .063       0  4747.8    .035       0    4985    .035       0
  5006.8    .035       0  5113.8     .07       0  5338.7      .1       0
  5503.9     .07       0  5570.1    .035       0
Bank Sta=4985,5006.8
XS Rating Curve= 0 ,0
Exp/Cntr=0.3,0.1

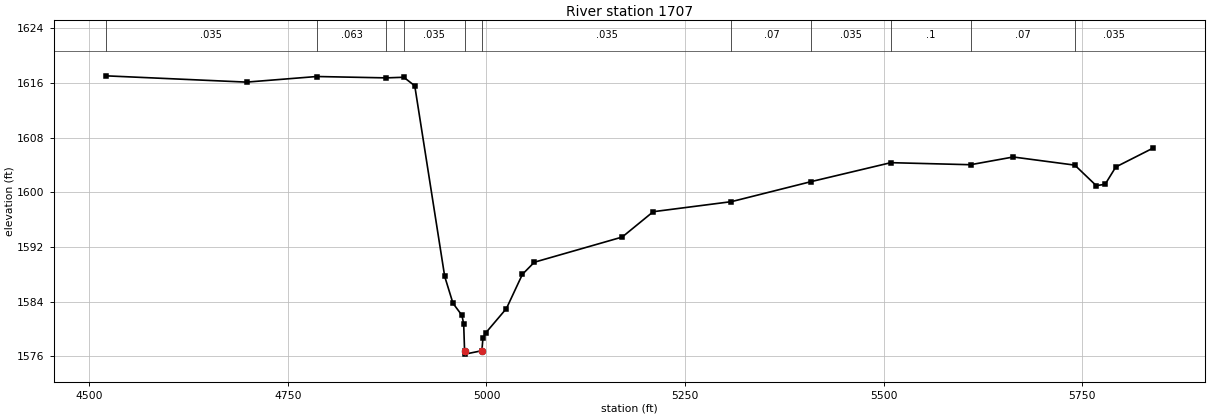
Type RM Length L Ch R = 1 ,1707    ,515,515,515
BEGIN DESCRIPTION:
Quinlan Creek 3.0
END DESCRIPTION:
XS GIS Cut Line= 3
      1927093.58     13922358.65        1926675.       13922125.
      1925856.37     13921942.05
#Sta/Elev= 30
  4520.9 1617.04  4697.9 1616.12  4786.4 1616.94  4873.7 1616.74  4895.9 1616.83
  4909.7 1615.58  4947.4  1587.7  4957.8 1583.78  4969.1 1582.01  4971.3 1580.73
  4972.4 1576.84  4972.9 1576.34  4994.2 1576.84  4995.5 1578.63    4999 1579.44
  5025.1 1583.01  5045.2 1588.01  5060.2 1589.78  5170.8 1593.46  5209.9 1597.17
  5308.4 1598.64  5408.7 1601.57    5509 1604.34  5609.3 1604.04  5663.1 1605.17
  5740.6 1603.98  5767.6 1600.98  5778.8 1601.18  5792.2 1603.71  5839.1 1606.47
#Mann= 11 ,-1 , 0
  4520.9    .035       0  4786.4    .063       0  4873.7    .094       0
  4895.9    .035       0  4972.4    .035       0  4994.2    .035       0
  5308.4     .07       0  5408.7    .035       0    5509      .1       0
  5609.3     .07       0  5740.6    .035       0
Bank Sta=4972.4,4994.2
XS Rating Curve= 0 ,0
Exp/Cntr=0.3,0.1