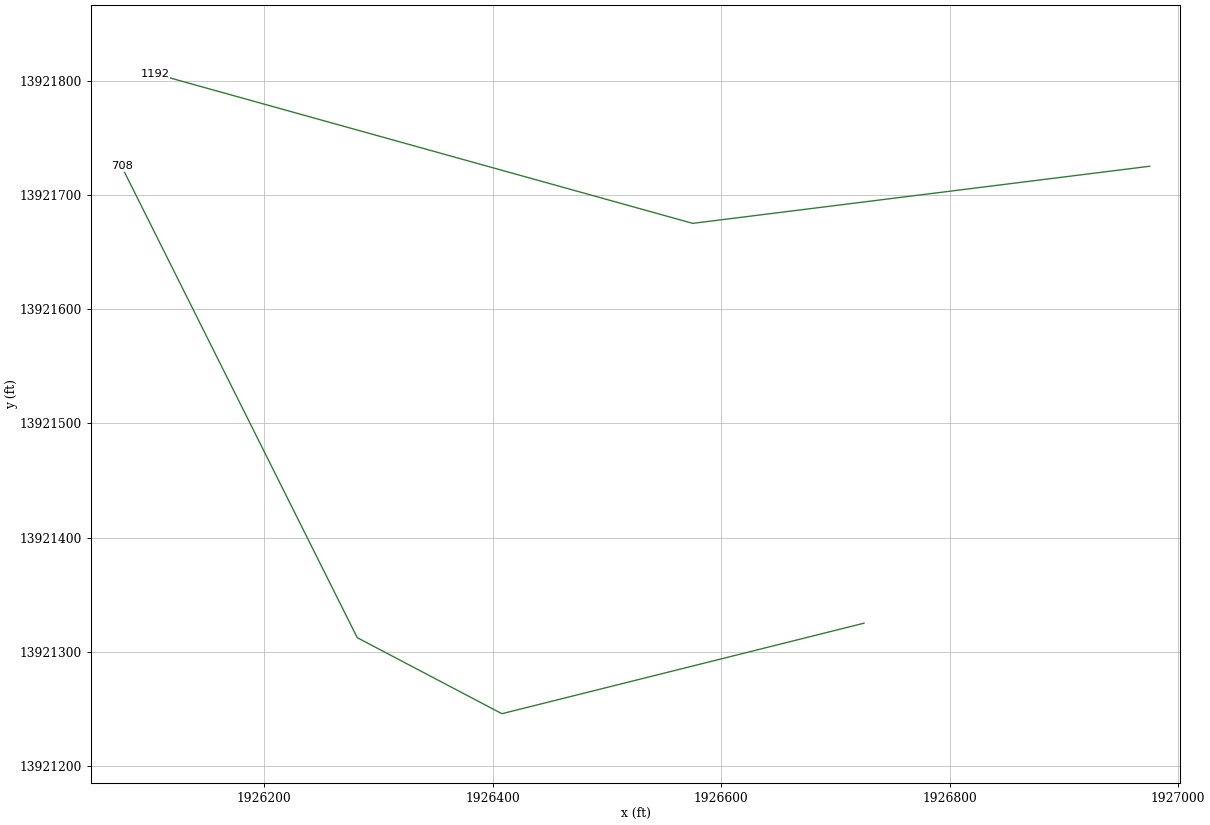
HEC-RAS study Quinlan Creek.prj: Quinlan Creek Base Level Engineering

--- Quinlan Creek.g01 (geometry) --- (continued)

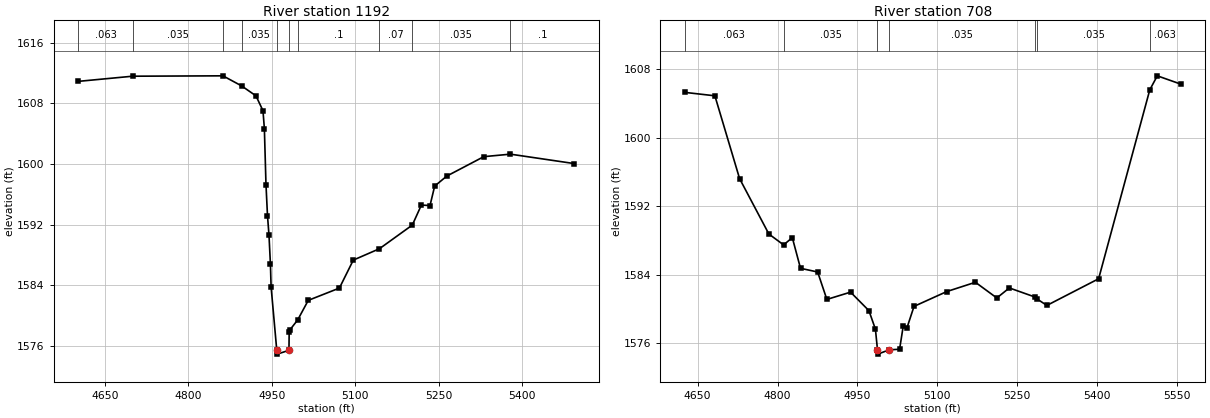
Type RM Length L Ch R = 1 ,1192    ,484,484,484
BEGIN DESCRIPTION:
Quinlan Creek 2.0
END DESCRIPTION:
XS GIS Cut Line= 3
      1926975.03       13921725.        1926575.       13921675.
      1926104.52      13921805.9
#Sta/Elev= 30
  4602.3 1610.88  4699.9 1611.56  4862.3 1611.61  4895.7 1610.29  4921.7 1608.97
  4934.3 1607.01  4936.8 1604.65  4939.7 1597.27  4942.4 1593.18  4945.1  1590.6
  4947.7 1586.76  4948.9 1583.77  4959.1 1575.41  4959.6 1574.91    4981 1575.41
  4981.4 1577.86  4982.1 1578.05  4996.7 1579.42  5015.7    1582  5071.7 1583.62
  5096.7 1587.31  5143.7 1588.81  5202.8 1591.93  5219.1 1594.57  5234.6  1594.5
    5243 1597.07  5264.8 1598.39  5331.3 1600.95  5379.1 1601.28  5493.8 1600.04
#Mann= 10 ,-1 , 0
  4602.3    .063       0  4699.9    .035       0  4862.3    .063       0
  4895.7    .035       0  4959.1     .05       0    4981    .035       0
  4996.7      .1       0  5143.7     .07       0  5202.8    .035       0
  5379.1      .1       0
Bank Sta=4959.1,4981
XS Rating Curve= 0 ,0
Exp/Cntr=0.3,0.1

Type RM Length L Ch R = 1 ,708     ,0,0,0
BEGIN DESCRIPTION:
Quinlan Creek 1.0
END DESCRIPTION:
XS GIS Cut Line= 4
      1926724.95     13921324.99        1926408.     13921245.75
      1926281.34     13921312.33      1926074.99     13921725.01
#Sta/Elev= 30
  4625.8 1605.29  4682.3 1604.89  4728.7 1595.23  4783.7 1588.77  4811.4  1587.5
  4827.7 1588.35  4843.1 1584.77  4875.3 1584.34  4892.6 1581.14  4937.1 1581.99
  4971.6 1579.83  4983.8 1577.67  4987.7 1575.26  4988.2 1574.76  5009.6 1575.26
  5029.2 1575.33    5036 1578.02  5042.7 1577.76  5056.3 1580.33  5117.9 1582.06
  5171.6 1583.14  5211.8 1581.31  5235.3 1582.48  5282.6 1581.44  5287.7 1581.18
  5305.8 1580.44    5403 1583.55  5499.1 1605.59  5513.2 1607.22    5557 1606.26
#Mann= 7 ,-1 , 0
  4625.8    .063       0  4811.4    .035       0  4987.7    .035       0
  5009.6    .035       0  5282.6    .063       0  5287.7    .035       0
  5499.1    .063       0
Bank Sta=4987.7,5009.6
XS Rating Curve= 0 ,0
Exp/Cntr=0.3,0.1

Chan Stop Cuts=-1
Use User Specified Reach Order=0
Composite Channel Slope=5