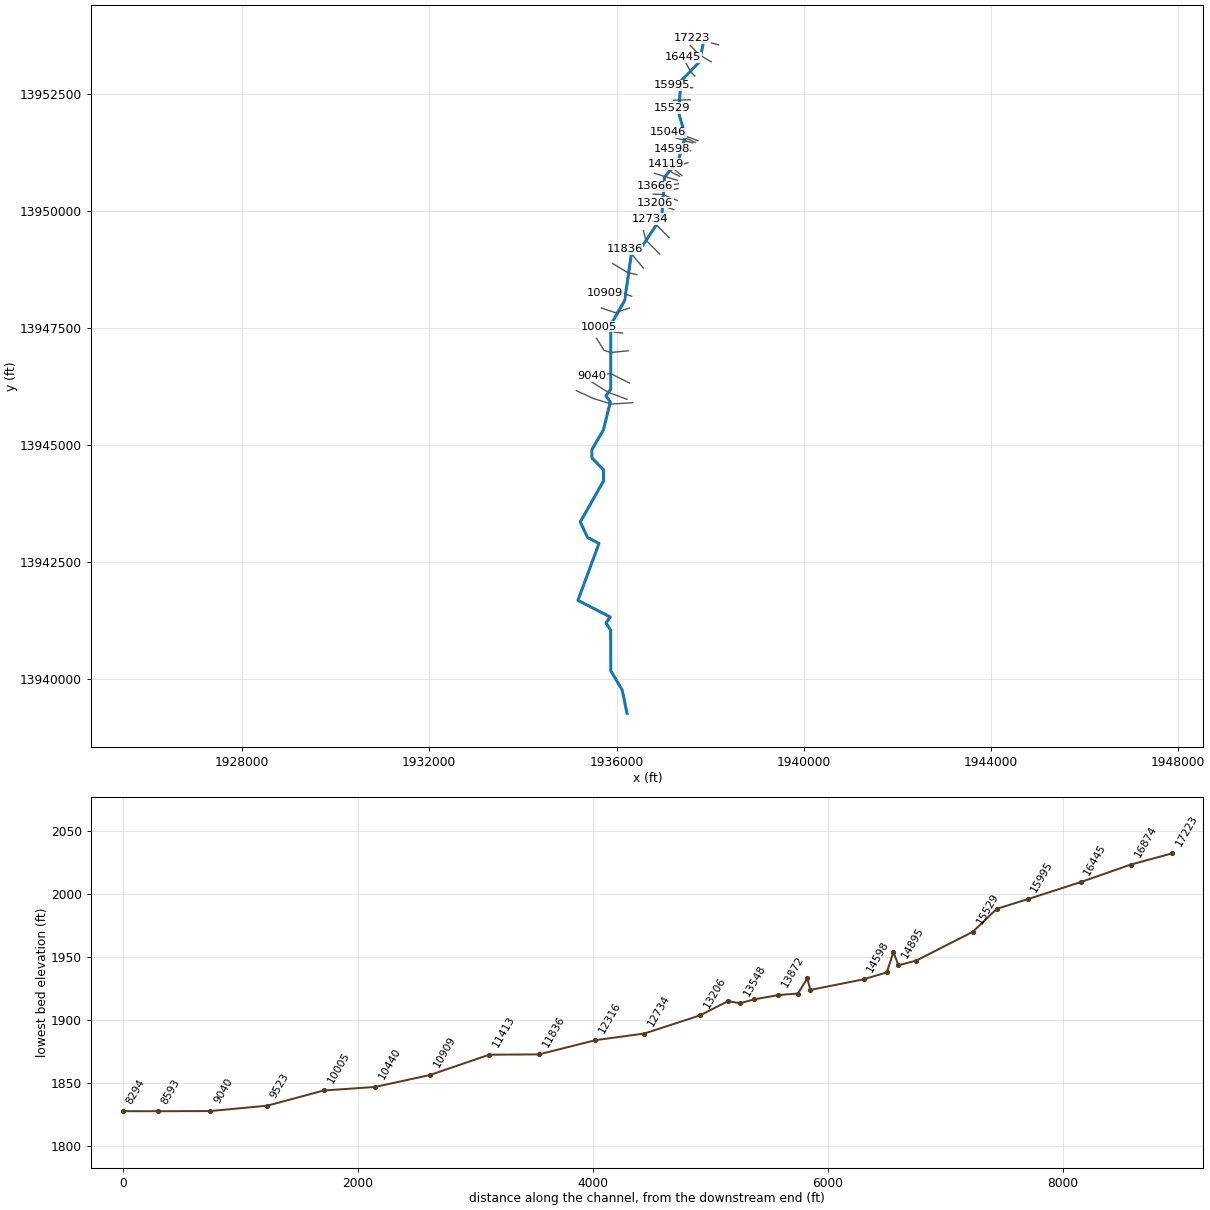
--- Rattlesnake Creek.prj (project) ---

Proj Title=Rattlesnake Creek Base Level Engineering
Current Plan=p01
Default Exp/Contr=0.3,0.1
English Units
Geom File=g01
Flow File=f01
Plan File=p01
Y Axis Title=Elevation
X Axis Title(PF)=Main Channel Distance
X Axis Title(XS)=Station
BEGIN DESCRIPTION:
Rattlesnake Creek
END DESCRIPTION:
DSS Export Rating Curves= 0
DSS Export Rating Curve Sorted= 0
DSS Export Volume Flow Curves= 0
DXF OffsetX= 0
DXF OffsetY= 0
DXF ScaleX= 1
DXF ScaleY= 10

--- Rattlesnake Creek.p01 (plan) ---

Plan Title=Multiple Run
Short Identifier=Multiple
Geom File=g01
Flow File=f01
Subcritical Flow
K Sum by GR= 0
Std Step Tol= 0.01
Critical Tol= 0.01
Num of Std Step Trials= 20
Max Error Tol= 0.3
Flow Tol Ratio= 0.001
Split Flow NTrial= 30
Split Flow Tol= 0.02
Split Flow Ratio= 0.02
Log Output Level= 0
Friction Slope Method= 1
Unsteady Friction Slope Method= 2
Unsteady Bridges Friction Slope Method= 1
Parabolic Critical Depth
Global Vel Dist=  1 , 1 , 1
Global Log Level= 0
CheckData=True
Encroach Param= -1, 0, 0, 0
BEGIN DESCRIPTION:
Multiple Run
END DESCRIPTION:

--- Rattlesnake Creek.f01 (steady flow) ---

Flow Title=Multiple
Program Version=4.10
Number of Profiles= 7
Profile Names=10-year,25-year,50-year,1pct_min,100-year,1pct_plu,500-year
River Rch & RM=Rattlesnake Cree,Reach-1         ,17223
     210     317     408     256     511    1020     786
River Rch & RM=Rattlesnake Cree,Reach-1         ,16445
     634    1046    1427     944    1884    3759    3234
River Rch & RM=Rattlesnake Cree,Reach-1         ,13872
     772    1288    1771    1180    2354    4697    4100
River Rch & RM=Rattlesnake Cree,Reach-1         ,11836
    1856    3272    4663    3210    6404   12778   11933
River Rch & RM=Rattlesnake Cree,Reach-1         ,9040
    1893    3332    4745    3262    6508   12986   12099
River Rch & RM=Rattlesnake Cree,Reach-1         ,7010
    2055    3635    5192    3580    7143   14251   13356
River Rch & RM=Rattlesnake Cree,Reach-1         ,6920
    2243    3977    5691    3928    7838   15638   14694
River Rch & RM=Rattlesnake Cree,Reach-1         ,4511
    3515    6360    9221    6438   12846   25631   24654
Boundary for River Rch & Prof#=Rattlesnake Cree,Reach-1         , 1
Up Type= 0
Dn Type= 3
Dn Slope=0.009
Boundary for River Rch & Prof#=Rattlesnake Cree,Reach-1         , 2
Up Type= 0
Dn Type= 3
Dn Slope=0.009
Boundary for River Rch & Prof#=Rattlesnake Cree,Reach-1         , 3
Up Type= 0
Dn Type= 3
Dn Slope=0.009
Boundary for River Rch & Prof#=Rattlesnake Cree,Reach-1         , 4
Up Type= 0
Dn Type= 3
Dn Slope=0.009
Boundary for River Rch & Prof#=Rattlesnake Cree,Reach-1         , 5
Up Type= 0
Dn Type= 3
Dn Slope=0.009
Boundary for River Rch & Prof#=Rattlesnake Cree,Reach-1         , 6
Up Type= 0
Dn Type= 3
Dn Slope=0.009
Boundary for River Rch & Prof#=Rattlesnake Cree,Reach-1         , 7
Up Type= 0
Dn Type= 3
Dn Slope=0.009
DSS Import GetInterval= 0
DSS Import GetPeak= 0
DSS Import FillOption= 0

--- Rattlesnake Creek.g01 (geometry) ---

Geom Title=Existing Conditions
Program Version=4.10

River Reach=Rattlesnake Cree,Reach-1
Reach XY= 30
        1937875.       13953675.      1937769.53     13953172.55
      1937377.24     13952769.07      1937324.91      13952095.1
      1937474.91     13951590.39      1937319.46     13951072.58
      1937027.06     13950719.15      1936967.21     13949871.58
      1936561.39     13949261.76        1936325.       13949125.
      1936172.93     13948080.86      1935877.26     13947569.06
      1935875.32     13946195.16      1935774.42       13946050.
      1935867.47     13945921.43      1935721.47     13945326.47
      1935474.73     13944900.31        1935475.       13944725.
      1935721.25     13944473.45       1935723.8      13944235.5
       1935225.5     13943359.78      1935380.09     13943030.05
      1935625.14     13942899.63      1935176.51     13941686.87
      1935866.04     13941331.69       1935774.5     13941200.03
      1935874.74     13941054.72      1935876.22      13940185.5
      1936121.24     13939773.44        1936225.       13939275.

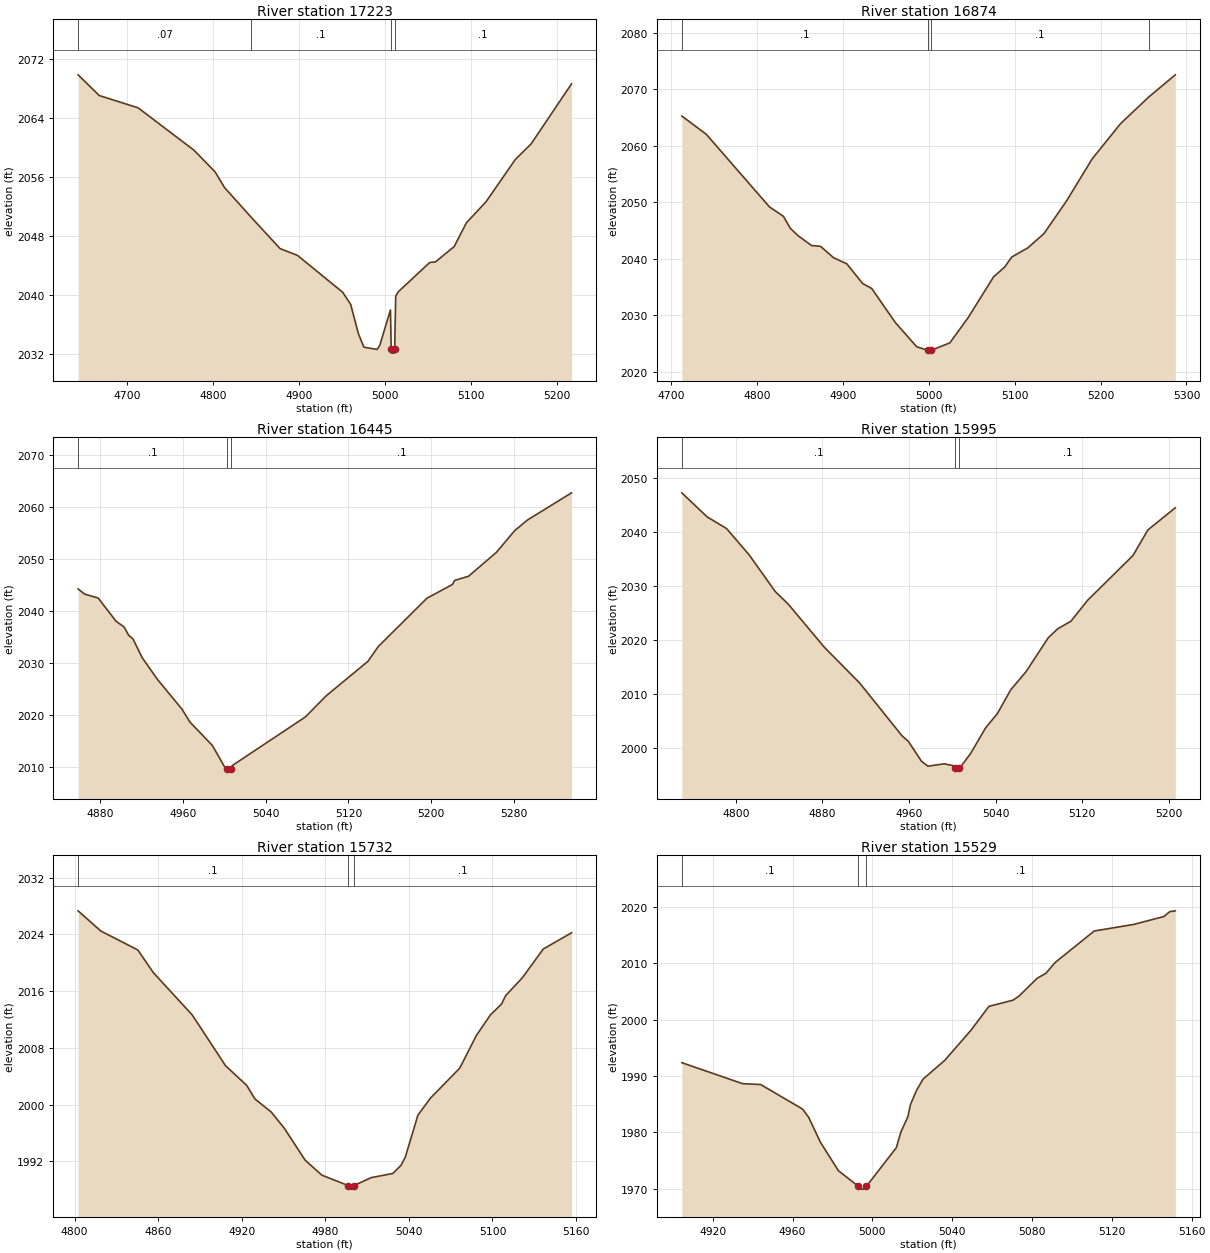
Type RM Length L Ch R = 1 ,17223   ,349,349,349
BEGIN DESCRIPTION:
Rattlesnake Creek 38.0
END DESCRIPTION:
XS GIS Cut Line= 2
      1938176.35      13953543.1      1937618.97     13953678.54
#Sta/Elev= 30
  4643.2  2069.9  4667.8 2067.09    4713 2065.42  4777.8 2059.68  4802.5 2056.72
  4813.4  2054.6    4844 2050.62    4878 2046.31  4898.2 2045.39  4950.7 2040.39
    4960 2038.75  4969.2 2034.71  4975.4 2032.93  4990.8 2032.62  4993.9 2033.18
  5006.3 2037.99  5007.2 2032.62  5007.4 2032.12  5010.9 2032.12  5011.2 2032.62
  5012.4 2039.85  5015.5 2040.46  5051.9 2044.42  5058.7 2044.51  5080.4 2046.59
  5094.5  2049.8  5117.4 2052.67  5151.4  2058.4  5169.9 2060.54  5216.8 2068.68
#Mann= 4 ,-1 , 0
  4643.2     .07       0    4844      .1       0  5007.2     .05       0
  5011.2      .1       0
Bank Sta=5007.2,5011.2
XS Rating Curve= 0 ,0
Exp/Cntr=0.3,0.1

Type RM Length L Ch R = 1 ,16874   ,429,429,429
BEGIN DESCRIPTION:
Rattlesnake Creek 37.0
END DESCRIPTION:
XS GIS Cut Line= 3
      1938025.03     13953174.98        1937775.       13953325.
      1937575.02     13953524.98
#Sta/Elev= 30
  4712.6  2065.3  4741.1 2062.06  4814.6 2049.19  4830.8 2047.53  4838.8 2045.42
  4847.7 2044.11  4863.6 2042.34  4874.1  2042.2  4889.3 2040.17  4904.6 2039.11
  4923.1 2035.61  4933.6 2034.73  4961.3 2028.66    4986  2024.4  4998.8 2023.77
  4999.1 2023.27  5002.6 2023.27  5002.8 2023.77  5024.6 2025.09  5045.8 2029.54
  5075.5 2036.79  5088.3 2038.51  5096.7 2040.31  5115.5 2041.94  5134.2 2044.47
  5160.4 2050.24  5190.1 2057.67  5223.3 2063.95  5256.2 2068.68    5287  2072.6
#Mann= 4 ,-1 , 0
  4712.6      .1       0  4998.8     .05       0  5002.8      .1       0
  5256.2     .07       0
Bank Sta=4998.8,5002.8
XS Rating Curve= 0 ,0
Exp/Cntr=0.3,0.1

Type RM Length L Ch R = 1 ,16445   ,450,450,450
BEGIN DESCRIPTION:
Rattlesnake Creek 36.0
END DESCRIPTION:
XS GIS Cut Line= 3
      1937675.01     13952874.99        1937575.       13952975.
      1937425.02     13953274.96
#Sta/Elev= 30
  4858.8 2044.34  4865.1 2043.34  4878.2 2042.59  4895.5 2038.12  4903.3 2037.01
  4907.5 2035.46  4911.8 2034.73  4920.9 2031.06  4935.4 2026.95  4959.1 2021.23
  4966.9 2018.72  4988.5 2014.24  5001.2 2009.82  5002.6 2009.79  5002.9 2009.29
  5006.4 2009.29  5006.6 2009.79    5008 2010.39  5078.4 2019.71  5098.5 2023.77
  5138.8  2030.4  5148.8 2033.24  5195.8 2042.54  5220.4 2045.18  5222.6 2045.97
    5236 2046.77  5262.9 2051.35  5280.8 2055.58  5293.1  2057.6  5335.6 2062.82
#Mann= 3 ,-1 , 0
  4858.8      .1       0  5002.6     .05       0  5006.6      .1       0
Bank Sta=5002.6,5006.6
XS Rating Curve= 0 ,0
Exp/Cntr=0.3,0.1

Type RM Length L Ch R = 1 ,15995   ,263,263,263
BEGIN DESCRIPTION:
Rattlesnake Creek 35.0
END DESCRIPTION:
XS GIS Cut Line= 3
      1937624.98       13952625.        1937375.       13952625.
      1937175.03     13952674.99
#Sta/Elev= 30
    4750 2047.17  4773.3 2042.74  4791.4 2040.56  4812.4 2035.66  4836.4 2028.91
  4848.4 2026.59  4881.4  2018.7  4914.4 2012.01  4953.4 2002.29  4959.4 2001.23
  4971.4 1997.59  4977.4 1996.64  4992.4 1997.08  5001.5 1996.72  5002.6 1996.23
  5002.8 1995.73  5006.3 1995.73  5006.6 1996.23  5016.9 1998.98  5030.8 2003.73
  5041.7 2006.38    5054 2010.76  5068.1  2014.1  5088.7 2020.38  5097.3 2022.02
  5109.7 2023.45  5125.2 2027.34    5167 2035.58  5180.8 2040.32  5206.1  2044.4
#Mann= 3 ,-1 , 0
    4750      .1       0  5002.6     .05       0  5006.6      .1       0
Bank Sta=5002.6,5006.6
XS Rating Curve= 0 ,0
Exp/Cntr=0.3,0.1

Type RM Length L Ch R = 1 ,15732   ,203,203,203
BEGIN DESCRIPTION:
Rattlesnake Creek 35.1
END DESCRIPTION:
XS GIS Cut Line= 2
      1937572.45     13952367.74       1937218.3     13952357.32
#Sta/Elev= 30
  4802.5 2027.31  4818.7 2024.48  4845.4 2021.79  4856.6 2018.58  4884.4 2012.65
  4908.4 2005.47  4923.5 2002.72  4929.4 2000.81  4941.2 1998.94  4950.5 1996.68
  4965.5 1992.17  4977.5 1990.05  4996.5 1988.58  4996.7 1988.08  5000.2 1988.08
  5000.5 1988.58  5012.9  1989.7  5028.5 1990.29  5034.4 1991.45  5037.4 1992.57
  5046.5 1998.51  5055.5 2000.91  5076.5 2005.13  5088.5 2009.75  5098.6 2012.65
  5106.5 2014.16  5109.5 2015.36  5121.5 2017.88  5136.5 2021.93  5156.8 2024.21
#Mann= 3 ,-1 , 0
  4802.5      .1       0  4996.5     .05       0  5000.5      .1       0
Bank Sta=4996.5,5000.5
XS Rating Curve= 0 ,0
Exp/Cntr=0.3,0.1

Type RM Length L Ch R = 1 ,15529   ,483,483,483
BEGIN DESCRIPTION:
Rattlesnake Creek 34.0
END DESCRIPTION:
XS GIS Cut Line= 3
      1937425.01       13952175.        1937325.       13952175.
      1937178.87     13952193.39
#Sta/Elev= 30
  4904.5 1992.34    4935 1988.61    4944 1988.46    4965 1984.11    4968 1982.68
    4974 1978.19    4983 1973.15    4993 1970.39  4993.2 1969.89  4996.7 1969.89
    4997 1970.39    5012 1977.25  5014.3 1980.05  5017.8 1982.74  5019.1 1984.93
  5022.1 1987.41  5025.4 1989.43  5036.2 1992.73  5049.3 1998.05  5058.4 2002.34
  5070.5 2003.44  5073.5 2004.17  5082.6 2007.33    5087 2008.22  5091.6 2010.13
  5111.2 2015.72    5131 2016.89  5146.1 2018.29    5149 2019.15  5151.8  2019.3
#Mann= 3 ,-1 , 0
  4904.5      .1       0    4993     .05       0    4997      .1       0
Bank Sta=4993,4997
XS Rating Curve= 0 ,0
Exp/Cntr=0.3,0.1

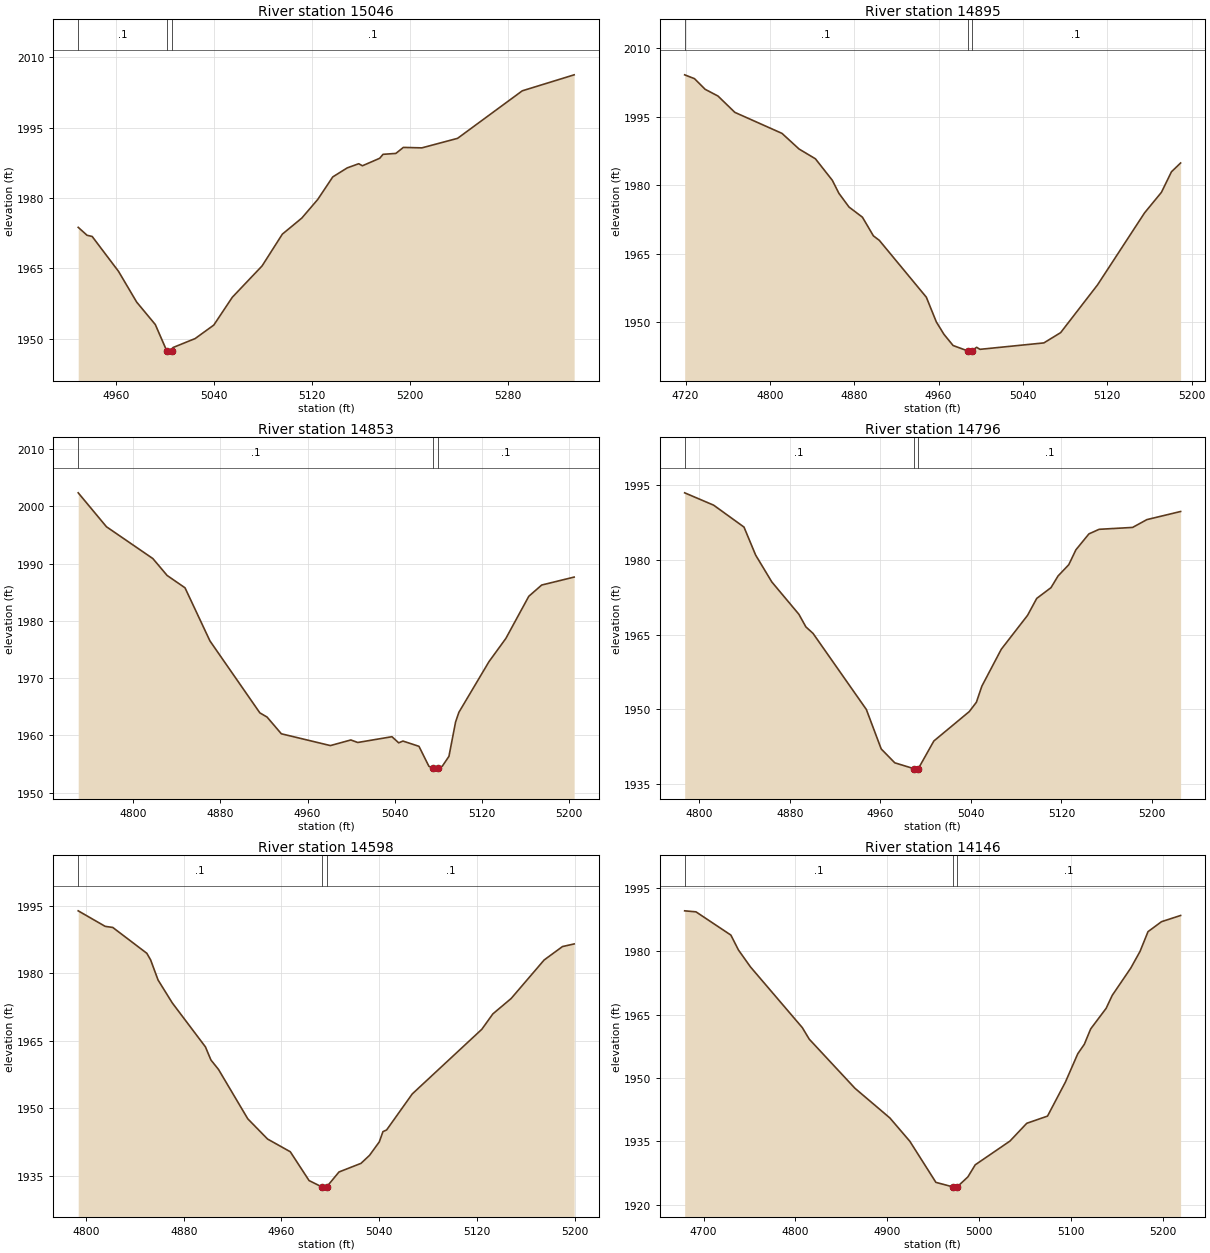
Type RM Length L Ch R = 1 ,15046   ,151,151,151
BEGIN DESCRIPTION:
Rattlesnake Creek 33.0
END DESCRIPTION:
XS GIS Cut Line= 3
        1937475.       13951775.        1937425.       13951725.
      1937094.66      13951677.1
#Sta/Elev= 30
  4929.3 1973.76  4936.5 1972.07  4940.7 1971.81  4962.2 1964.36    4977 1957.81
  4992.2 1953.02  5001.5 1947.43  5001.7 1946.93  5005.2 1946.93  5005.5 1947.43
  5006.5 1948.11  5024.7 1950.04  5039.9 1952.92    5055 1958.85  5079.3 1965.54
  5095.8 1972.31  5111.7 1975.74  5124.7 1979.72  5136.9 1984.51  5148.7 1986.44
  5158.1 1987.33  5161.1 1986.89  5175.2 1988.49  5177.9 1989.33  5188.4 1989.53
  5194.5 1990.81  5209.6 1990.71  5238.7 1992.74  5291.5 2002.88  5333.8 2006.29
#Mann= 3 ,-1 , 0
  4929.3      .1       0  5001.5     .05       0  5005.5      .1       0
Bank Sta=5001.5,5005.5
XS Rating Curve= 0 ,0
Exp/Cntr=0.3,0.1

Type RM Length L Ch R = 1 ,14895   ,42,42,42
BEGIN DESCRIPTION:
Mapping XS 4e7e1950
END DESCRIPTION:
XS GIS Cut Line= 2
      1937739.35     13951495.98      1937296.37     13951654.24
#Sta/Elev= 30
  4719.2 2004.22  4728.5 2003.38  4738.6 2001.05  4750.8 1999.57  4766.8 1995.99
  4811.5 1991.39  4827.7 1987.96  4843.2 1985.82  4859.2 1981.12  4865.5 1978.25
  4875.1 1975.24  4887.8 1973.02  4898.2 1968.93  4903.8 1967.95  4948.4 1955.49
  4957.9 1950.07  4965.1 1947.36  4973.8  1944.9  4987.5 1943.73  4987.8 1943.23
  4991.5 1943.73  4996.1 1944.51  4999.3 1944.06  5059.9 1945.47  5075.8 1947.72
  5110.8 1958.19  5155.4 1973.97  5171.4 1978.47  5180.9 1982.97  5189.6  1984.9
#Mann= 3 ,-1 , 0
  4719.2      .1       0  4987.5     .05       0  4991.5      .1       0
Bank Sta=4987.5,4991.5
XS Rating Curve= 0 ,0
Exp/Cntr=0.3,0.1

Type RM Length L Ch R = 1 ,14853   ,57,57,57
BEGIN DESCRIPTION:
Rattlesake Creek 32.5
END DESCRIPTION:
XS GIS Cut Line= 4
      1937685.31       13951458.      1937490.83     13951543.08
      1937405.76     13951569.13      1937254.76     13951598.63
#Sta/Elev= 30
  4749.5 2002.34  4775.4 1996.42    4818 1990.86  4831.1 1987.91  4847.5 1985.76
  4870.4 1976.48  4916.2 1963.92  4922.8 1963.19  4935.9 1960.27  4980.9 1958.21
  4999.7 1959.19    5006 1958.75  5037.4 1959.76  5043.6 1958.69  5047.5    1959
  5062.2 1958.08  5071.3  1954.6  5075.4 1954.25  5075.7 1953.75  5079.2 1953.75
  5079.4 1954.25  5083.6 1954.61  5089.7 1956.33  5095.8 1962.33  5098.8 1964.01
  5126.4 1972.85  5141.9 1976.91    5163 1984.28  5174.8 1986.24  5204.6 1987.63
#Mann= 3 ,-1 , 0
  4749.5      .1       0  5075.4     .05       0  5079.4      .1       0
Bank Sta=5075.4,5079.4
XS Rating Curve= 0 ,0
Exp/Cntr=0.3,0.1

Type RM Length L Ch R = 1 ,14796   ,198,198,198
BEGIN DESCRIPTION:
Mapping XS cb891b0a
END DESCRIPTION:
XS GIS Cut Line= 2
      1937629.02      13951445.6      1937210.04     13951573.63
#Sta/Elev= 30
  4787.2 1993.51  4812.8 1991.03  4839.6 1986.63  4849.9    1981  4864.2  1975.6
  4888.1 1969.11  4894.3 1966.57  4900.6 1965.27  4947.7 1949.98  4960.8 1942.06
  4972.8 1939.27  4989.6  1938.1  4989.8  1937.6  4993.6  1938.1  5007.3 1943.65
  5038.6 1949.56  5044.9 1951.44  5049.7 1954.66  5066.9 1962.09  5090.1  1968.9
  5098.2  1972.3  5110.8 1974.46    5117  1976.8  5126.5 1979.07  5132.8 1982.06
  5144.3 1985.26  5153.3 1986.18  5182.9 1986.56  5195.5 1988.13  5225.3 1989.76
#Mann= 3 ,-1 , 0
  4787.2      .1       0  4989.6     .05       0  4993.6      .1       0
Bank Sta=4989.6,4993.6
XS Rating Curve= 0 ,0
Exp/Cntr=0.3,0.1

Type RM Length L Ch R = 1 ,14598   ,452,452,452
BEGIN DESCRIPTION:
Rattlesnake Creek 32.0
END DESCRIPTION:
XS GIS Cut Line= 3
      1937575.03     13951274.99        1937375.       13951325.
      1937174.99       13951325.
#Sta/Elev= 30
  4793.5 1993.87  4815.6 1990.42  4821.8 1990.18  4849.7 1984.44  4852.8 1982.98
  4858.9 1978.51  4870.5 1973.44  4897.7 1963.66  4902.2 1960.75  4908.4 1958.65
  4932.4 1947.68  4948.6 1943.19  4967.2 1940.37  4982.6 1933.97    4993 1932.57
  4993.2 1932.07    4997 1932.57  5007.1 1935.88  5025.1 1937.79  5032.1 1939.57
  5040.1 1942.56  5043.1 1944.84  5046.1 1945.21  5067.1 1953.21  5124.1 1967.57
  5133.1 1970.98  5148.1  1974.4  5175.1 1982.95  5190.1 1985.93  5199.7 1986.52
#Mann= 3 ,-1 , 0
  4793.5      .1       0    4993     .05       0    4997      .1       0
Bank Sta=4993,4997
XS Rating Curve= 0 ,0
Exp/Cntr=0.3,0.1

Type RM Length L Ch R = 1 ,14146   ,27,27,27
BEGIN DESCRIPTION:
Rattlesnake Creek 31.0
END DESCRIPTION:
XS GIS Cut Line= 3
      1937525.03     13951025.01        1937225.       13950925.
      1937024.97     13951025.01
#Sta/Elev= 30
  4679.4 1989.54  4691.7  1989.3  4729.7  1983.8  4737.9 1980.29    4751 1976.27
  4807.5 1961.89    4815 1959.17  4864.8 1947.54  4902.8 1940.52  4924.5 1935.01
  4952.9 1925.28  4971.9 1924.18  4972.2 1923.68  4975.9 1924.18  4987.7 1926.57
  4995.7 1929.43  5033.5 1935.05  5051.8 1939.26  5074.4 1940.96  5093.9 1949.02
  5107.3  1955.7  5114.5 1957.97  5121.4  1961.6  5138.2 1966.46  5144.9 1969.55
    5165 1975.98  5175.1 1979.93  5183.8 1984.61  5198.5 1986.97  5219.3 1988.44
#Mann= 3 ,-1 , 0
  4679.4      .1       0  4971.9     .05       0  4975.9      .1       0
Bank Sta=4971.9,4975.9
XS Rating Curve= 0 ,0
Exp/Cntr=0.3,0.1

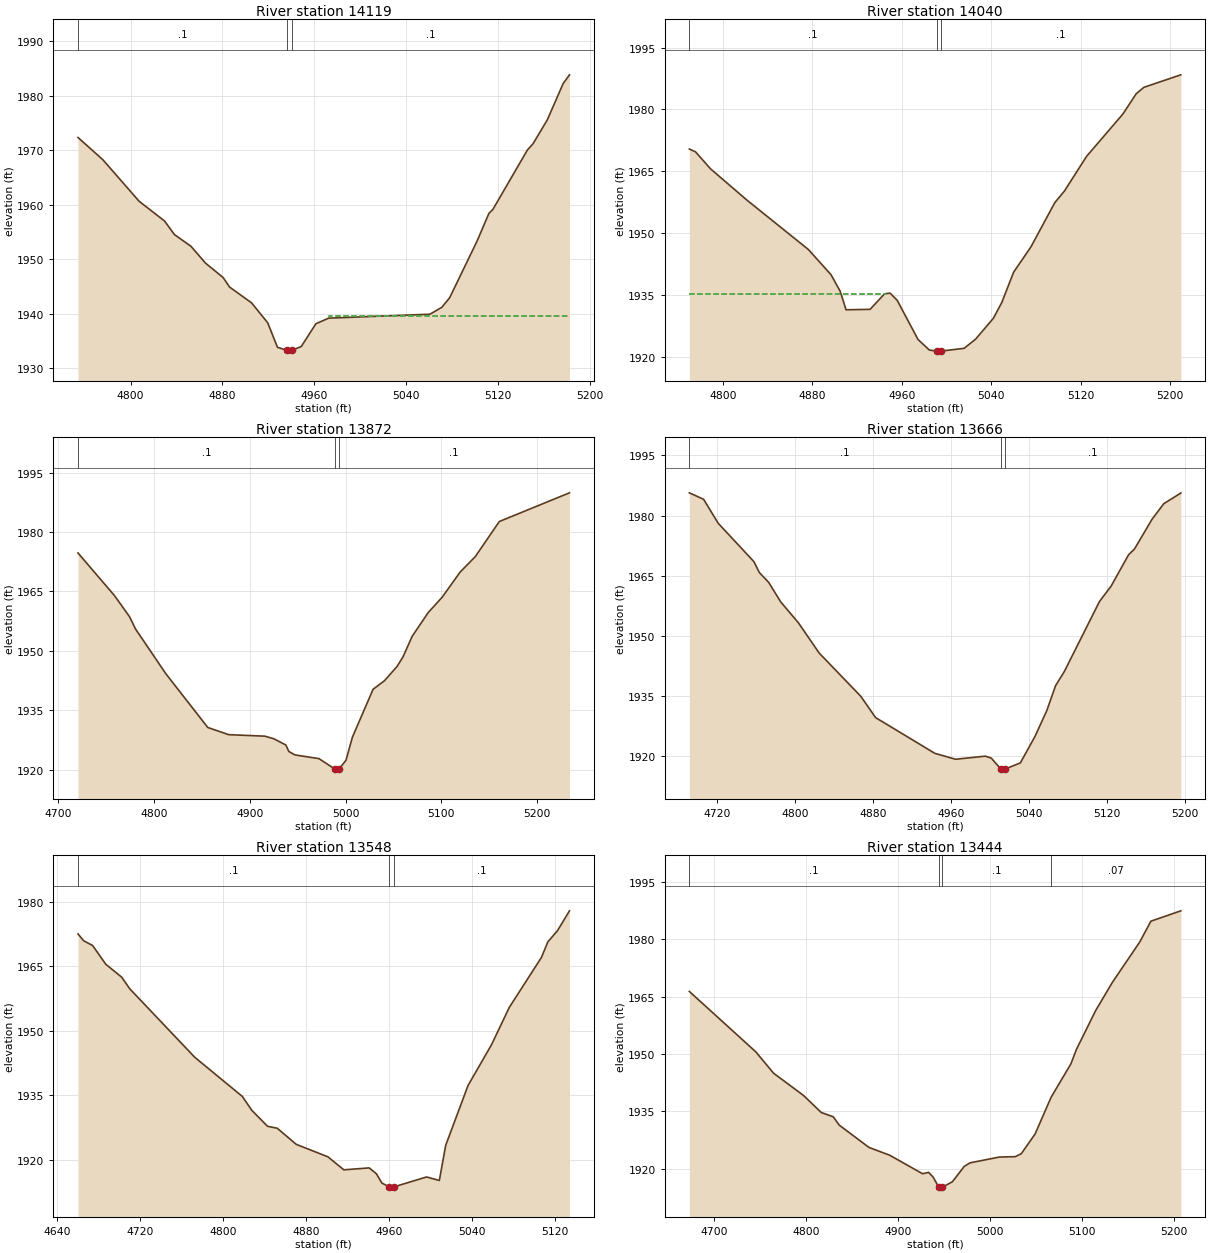
Type RM Length L Ch R = 1 ,14119   ,79,79,79
BEGIN DESCRIPTION:
Rattlesnake Creek 31.1
END DESCRIPTION:
XS GIS Cut Line= 3
      1937397.08     13950751.42      1937187.01     13950919.82
      1937048.17     13950996.19
#Sta/Elev= 30
  4754.3 1972.32  4775.9 1968.25  4807.5 1960.62  4829.7 1956.98  4838.2 1954.51
  4852.6 1952.36  4865.2 1949.28  4880.6 1946.62  4886.2 1944.88  4905.4 1941.97
  4919.4 1938.32  4927.9 1933.82  4936.3 1933.25  4936.5 1932.75    4940 1932.75
  4940.3 1933.25  4948.6 1933.96  4961.3 1938.14  4972.5 1939.17  5060.6 1939.89
  5070.9 1941.16  5077.7  1942.9  5101.7 1953.36  5111.9 1958.39  5115.4 1959.14
  5145.4 1970.03  5150.3 1971.17  5162.8 1975.59  5176.4 1982.17    5182 1983.82
#Mann= 3 ,-1 , 0
  4754.3      .1       0  4936.3     .05       0  4940.3      .1       0
#XS Ineff= 2 , 0
                         4972.98         1939.63
Permanent Ineff=
       F       F
Bank Sta=4936.3,4940.3
XS Rating Curve= 0 ,0
Exp/Cntr=0.3,0.1

Type RM Length L Ch R = 1 ,14040   ,168,168,168
BEGIN DESCRIPTION:
Mapping XS ec9cd0aa
END DESCRIPTION:
XS GIS Cut Line= 3
      1937348.48     13950735.48      1937200.76     13950810.61
      1936981.05     13950974.27
#Sta/Elev= 30
  4769.9 1970.37  4775.4 1969.68  4788.9 1965.54  4821.6 1957.92  4876.4 1945.97
  4896.6 1939.87  4904.8 1935.86  4910.1 1931.34  4931.6 1931.45  4944.5 1935.21
  4949.5 1935.39  4955.8 1933.66  4974.5 1924.12  4984.7 1921.56  4991.3 1921.32
  4991.5 1920.82  4995.3 1921.32  5015.7 1921.99    5026 1924.21  5041.9 1929.28
  5049.4  1933.1    5060 1940.46  5075.6 1946.66  5096.8 1957.33  5105.4 1960.14
  5125.3 1968.59  5157.8 1978.87  5169.7 1983.78  5176.6 1985.34  5209.6 1988.37
#Mann= 3 ,-1 , 0
  4769.9      .1       0  4991.3     .05       0  4995.3      .1       0
#XS Ineff= 2 , 0
         4945.52 1935.29
Permanent Ineff=
       F       F
Bank Sta=4991.3,4995.3
XS Rating Curve= 0 ,0
Exp/Cntr=0.3,0.1

Type RM Length L Ch R = 1 ,13872   ,206,206,206
BEGIN DESCRIPTION:
Mapping XS 554ce20a
END DESCRIPTION:
XS GIS Cut Line= 2
      1937299.06     13950648.53      1936808.49     13950797.87
#Sta/Elev= 30
  4720.8 1974.71    4759  1963.9  4774.6  1958.6  4780.8 1955.52  4812.3 1944.25
  4856.2 1930.62  4878.1  1928.8  4915.8 1928.42  4925.2 1927.76  4937.7 1926.19
  4940.8 1924.55  4947.1 1923.69  4972.2 1922.75    4989 1920.09  4989.3 1919.59
  4992.8 1919.59    4993 1920.09  5000.4 1922.32  5007.1 1928.15  5028.7 1940.27
  5040.5 1942.41  5053.7 1946.03    5060  1948.5  5069.4 1953.62  5086.1 1959.61
  5100.8 1963.54  5119.6  1969.9  5135.3 1973.77  5160.4 1982.65  5233.6  1989.9
#Mann= 3 ,-1 , 0
  4720.8      .1       0    4989     .05       0    4993      .1       0
Bank Sta=4989,4993
XS Rating Curve= 0 ,0
Exp/Cntr=0.3,0.1

Type RM Length L Ch R = 1 ,13666   ,118,118,118
BEGIN DESCRIPTION:
Rattlesnake Creek 30.0
END DESCRIPTION:
XS GIS Cut Line= 3
      1937324.97     13950574.99        1937025.       13950525.
        1936825.       13950525.
#Sta/Elev= 30
  4691.3 1985.67  4705.9 1984.06  4720.9 1978.06  4757.6 1968.45    4763 1965.79
  4772.8 1963.25    4785 1958.42  4803.2 1953.18  4824.5 1945.62  4867.1 1934.84
  4882.3 1929.51  4943.1 1920.57  4964.4  1919.1  4994.8 1919.87  5000.9  1919.4
  5010.9 1916.63  5011.1 1916.13  5014.9 1916.63  5030.8 1918.19  5045.9 1924.84
  5057.9 1931.24  5066.9 1937.47  5075.9 1941.02  5111.9 1958.49  5123.9 1962.37
  5141.9 1970.23  5147.8 1971.61  5165.9 1979.08  5177.9 1982.95  5195.4 1985.62
#Mann= 3 ,-1 , 0
  4691.3      .1       0  5010.9     .05       0  5014.9      .1       0
Bank Sta=5010.9,5014.9
XS Rating Curve= 0 ,0
Exp/Cntr=0.3,0.1

Type RM Length L Ch R = 1 ,13548   ,104,104,104
BEGIN DESCRIPTION:
Mapping XS 3efc0e7e
END DESCRIPTION:
XS GIS Cut Line= 3
      1937312.95     13950473.02      1937018.44     13950415.23
      1936849.22     13950453.42
#Sta/Elev= 30
  4660.5 1972.51    4666 1970.91  4674.6 1969.81  4687.3 1965.45  4702.7 1962.42
  4710.3 1959.76    4773 1943.81  4818.9 1934.68    4828 1931.45  4843.2 1927.74
  4852.5 1927.29  4870.8 1923.54  4901.4 1920.63  4916.7 1917.61  4941.1 1918.06
    4948 1916.71  4953.4 1914.52  4960.6 1913.62  4960.8 1913.12  4964.6 1913.62
  4996.4 1915.95  5008.7 1915.13  5014.8 1923.29  5036.4 1937.26    5059 1946.73
  5076.1  1955.4  5107.1 1967.04  5113.3 1970.67  5122.5 1973.24  5134.1 1977.88
#Mann= 3 ,-1 , 0
  4660.5      .1       0  4960.6     .05       0  4964.6      .1       0
Bank Sta=4960.6,4964.6
XS Rating Curve= 0 ,0
Exp/Cntr=0.3,0.1

Type RM Length L Ch R = 1 ,13444   ,238,238,238
BEGIN DESCRIPTION:
Rattlesnake Creek 29.2
END DESCRIPTION:
XS GIS Cut Line= 4
      1937296.43     13950220.15      1937025.55     13950331.28
      1936976.94      13950346.9      1936786.01     13950353.85
#Sta/Elev= 30
  4672.7 1966.34    4745 1950.57  4764.3    1945  4796.9 1939.19  4816.3 1934.72
  4829.3 1933.61  4835.8 1931.43  4868.2  1925.6  4890.8 1923.56  4926.6 1918.72
  4933.1  1919.1  4938.2 1917.79  4944.1 1915.21  4944.3 1914.71  4948.1 1915.21
    4959 1916.64  4971.8 1920.63  4978.1 1921.57  5010.1 1923.09  5027.3 1923.19
  5033.9 1923.95    5049 1929.12  5066.4  1938.7    5088 1947.46    5094 1951.22
    5115  1961.4  5133.2 1968.75    5163  1979.3    5175 1984.69  5207.6  1987.4
#Mann= 4 ,-1 , 0
  4672.7      .1       0  4944.1     .05       0  4948.1      .1       0
  5066.4     .07       0
Bank Sta=4944.1,4948.1
XS Rating Curve= 0 ,0
Exp/Cntr=0.3,0.1

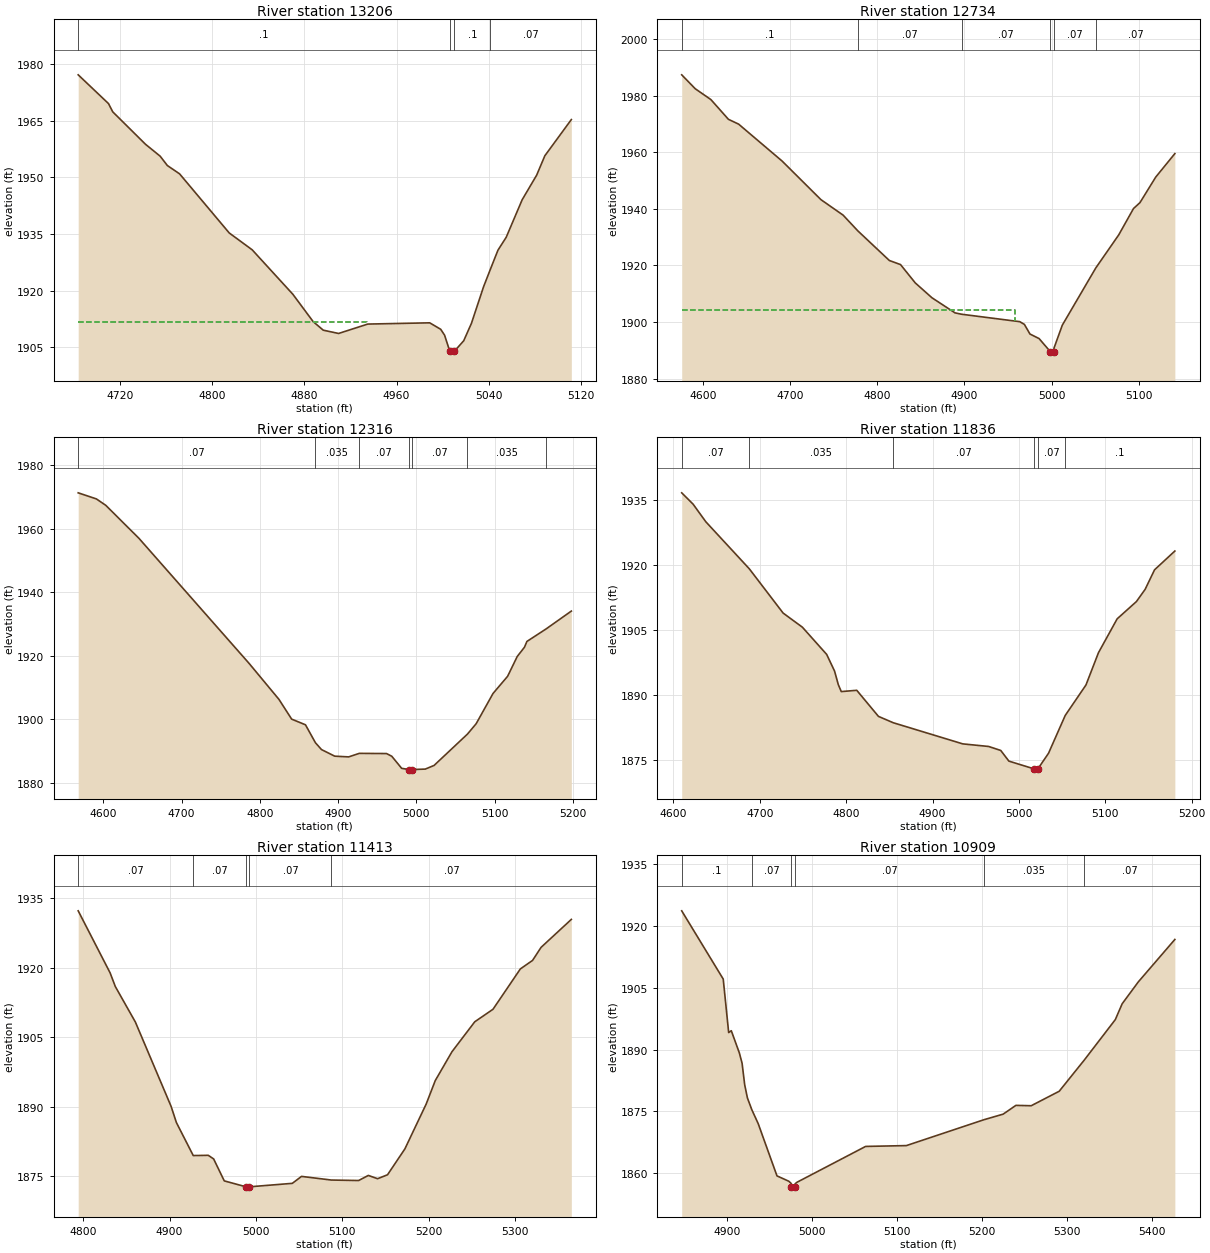
Type RM Length L Ch R = 1 ,13206   ,472,472,472
BEGIN DESCRIPTION:
Rattlesnake Creek 29.0
END DESCRIPTION:
XS GIS Cut Line= 3
      1937224.97     13950025.01        1936925.       13950125.
        1936825.       13950175.
#Sta/Elev= 30
  4683.7 1977.17    4710 1969.55  4713.7 1967.36  4742.1 1958.77  4754.8 1955.62
  4761.1 1953.13  4771.7 1950.93  4814.8 1935.26  4834.7  1930.8    4870 1919.02
  4887.6 1911.78  4896.4  1909.5  4909.7 1908.63    4935 1911.12  4988.8 1911.45
  4998.3 1909.74  5001.7 1908.17  5006.2 1903.92  5006.5 1903.42  5010.2 1903.92
  5018.3  1906.7    5025 1911.32  5035.5 1920.99  5041.4 1925.61    5048 1930.69
  5055.2 1934.14    5069 1944.05  5081.6 1950.58  5088.7 1955.72  5111.7 1965.31
#Mann= 4 ,-1 , 0
  4683.7      .1       0  5006.2     .05       0  5010.2      .1       0
  5041.4     .07       0
#XS Ineff= 2 , 0
         4934.31 1911.58
Permanent Ineff=
       F       F
Bank Sta=5006.2,5010.2
XS Rating Curve= 0 ,0
Exp/Cntr=0.3,0.1

Type RM Length L Ch R = 1 ,12734   ,418,418,418
BEGIN DESCRIPTION:
Rattlesnake Creek 28.0
END DESCRIPTION:
XS GIS Cut Line= 3
      1937125.01     13949424.99        1936825.       13949725.
        1936725.       13949825.
#Sta/Elev= 30
  4575.7 1987.35  4591.2 1982.44  4609.2  1978.6  4629.3 1971.63    4641 1969.93
  4690.9 1956.88  4735.4 1943.26  4760.9 1937.77  4777.7 1932.24  4813.9 1921.76
  4826.7 1920.32  4843.6 1913.85  4862.7 1908.61  4889.2 1903.26  4896.9 1902.77
  4963.5 1900.15  4968.8 1899.19  4975.2 1895.79  4985.7 1894.17  4998.6 1889.54
  4998.9 1889.04  5002.6 1889.54  5002.7 1890.76  5012.3 1898.92  5050.7 1919.13
    5077  1930.8    5094 1940.13  5101.4 1942.21  5119.4  1951.2  5141.4 1959.52
#Mann= 6 ,-1 , 0
  4575.7      .1       0  4777.7     .07       0  4896.9     .07       0
  4998.6     .05       0  5002.6     .07       0  5050.7     .07       0
#XS Ineff= 2 , 0
          4958.3 1904.32
Permanent Ineff=
       F       F
Bank Sta=4998.6,5002.6
XS Rating Curve= 0 ,0
Exp/Cntr=0.3,0.1

Type RM Length L Ch R = 1 ,12316   ,480,480,480
BEGIN DESCRIPTION:
Rattlesnake Creek 27.0
END DESCRIPTION:
XS GIS Cut Line= 3
      1936925.03     13949074.97        1936625.       13949375.
      1936574.99     13949575.03
#Sta/Elev= 30
  4567.7 1971.33    4591 1969.41    4603 1967.39  4645.4    1957  4786.2 1917.64
  4824.4 1906.31  4840.6  1900.1  4858.3 1898.31    4871 1892.67  4878.8 1890.51
  4895.7 1888.44  4913.5 1888.21  4927.1 1889.32  4961.9 1889.26  4968.6 1888.42
  4981.3  1884.6    4991 1884.23  4991.2 1883.73    4995 1884.23  5011.5 1884.37
  5022.7 1885.52  5065.4 1895.39  5076.5 1898.65  5098.1 1908.18  5116.7 1913.57
    5129  1919.8  5138.3 1922.75  5141.4 1924.55    5166  1928.5  5198.2 1934.11
#Mann= 7 ,-1 , 0
  4567.7     .07       0    4871    .035       0  4927.1     .07       0
    4991     .05       0    4995     .07       0  5065.4    .035       0
    5166     .07       0
Bank Sta=4991,4995
XS Rating Curve= 0 ,0
Exp/Cntr=0.3,0.1

Type RM Length L Ch R = 1 ,11836   ,423,423,423
BEGIN DESCRIPTION:
Rattlesnake Creek 26.0
END DESCRIPTION:
XS GIS Cut Line= 3
      1936574.98     13948775.03        1936325.       13949075.
      1936174.96     13949175.02
#Sta/Elev= 30
  4609.7  1936.7  4622.9 1934.08  4637.6 1930.02  4687.9 1919.17  4727.1 1908.94
  4749.4 1905.68  4777.5  1899.4  4786.6 1895.56    4791  1892.4  4794.4 1890.82
  4812.3 1891.12  4837.4  1885.1  4854.4 1883.64    4935 1878.75    4965 1878.15
    4979 1877.23  4988.4 1874.77  5017.9 1872.96  5018.2 1872.46  5021.7 1872.46
  5021.9 1872.96  5034.3 1876.59  5053.6 1885.31  5077.6 1892.34  5092.1  1899.8
  5113.7 1907.61    5136  1911.6  5146.1 1914.42    5157 1918.93  5180.5 1923.26
#Mann= 6 ,-1 , 0
  4609.7     .07       0  4687.9    .035       0  4854.4     .07       0
  5017.9     .05       0  5021.9     .07       0  5053.6      .1       0
Bank Sta=5017.9,5021.9
XS Rating Curve= 0 ,0
Exp/Cntr=0.3,0.1

Type RM Length L Ch R = 1 ,11413   ,504,504,504
BEGIN DESCRIPTION:
Rattlesnake Creek 25.0
END DESCRIPTION:
XS GIS Cut Line= 3
       1936434.5      13948636.7      1936231.43     13948682.53
      1935922.26     13948872.22
#Sta/Elev= 30
  4794.3  1932.3  4831.2 1918.92  4837.3 1915.94  4860.5 1908.28  4901.9 1890.05
    4908 1886.57  4927.5 1879.45  4944.9  1879.5  4951.1 1878.72  4963.4 1873.98
  4988.6  1872.7  4988.9  1872.2  4992.6  1872.7  5042.2 1873.45  5052.8 1874.95
  5087.5 1874.16    5119 1874.06  5130.2 1875.16  5140.9 1874.45  5152.4  1875.3
  5172.5 1880.89  5197.1 1890.55  5207.7 1895.65    5227 1901.87  5253.4 1908.34
  5274.5 1911.04  5306.2 1919.76  5320.3 1921.59  5330.2 1924.42  5365.2 1930.45
#Mann= 5 ,-1 , 0
  4794.3     .07       0  4927.5     .07       0  4988.6     .05       0
  4992.6     .07       0  5087.5     .07       0
Bank Sta=4988.6,4992.6
XS Rating Curve= 0 ,0
Exp/Cntr=0.3,0.1

Type RM Length L Ch R = 1 ,10909   ,469,469,469
BEGIN DESCRIPTION:
Rattlesnake Creek 24.0
END DESCRIPTION:
XS GIS Cut Line= 3
      1936324.99       13948175.        1936175.       13948225.
      1935752.43     13948235.43
#Sta/Elev= 30
  4846.2 1923.73  4895.1 1907.14  4901.5 1894.14  4904.6 1894.59  4914.1 1889.18
  4917.3 1886.68  4920.4 1881.41  4923.6 1878.24  4928.7 1875.42  4936.3 1871.99
  4958.4  1859.3  4972.4 1857.99  4975.1 1857.46  4975.4 1856.58  4975.6 1856.08
  4979.4 1856.58  4979.8 1857.38  4981.9 1857.74  5062.8 1866.46  5110.8 1866.66
    5202 1872.94  5224.8 1874.31  5239.8 1876.44  5257.8 1876.35  5290.8 1879.87
  5320.3 1887.45  5356.9 1897.29  5364.9 1901.12  5383.9 1906.44    5427 1916.77
#Mann= 6 ,-1 , 0
  4846.2      .1       0  4928.7     .07       0  4975.4     .05       0
  4979.4     .07       0    5202    .035       0  5320.3     .07       0
Bank Sta=4975.4,4979.4
XS Rating Curve= 0 ,0
Exp/Cntr=0.3,0.1

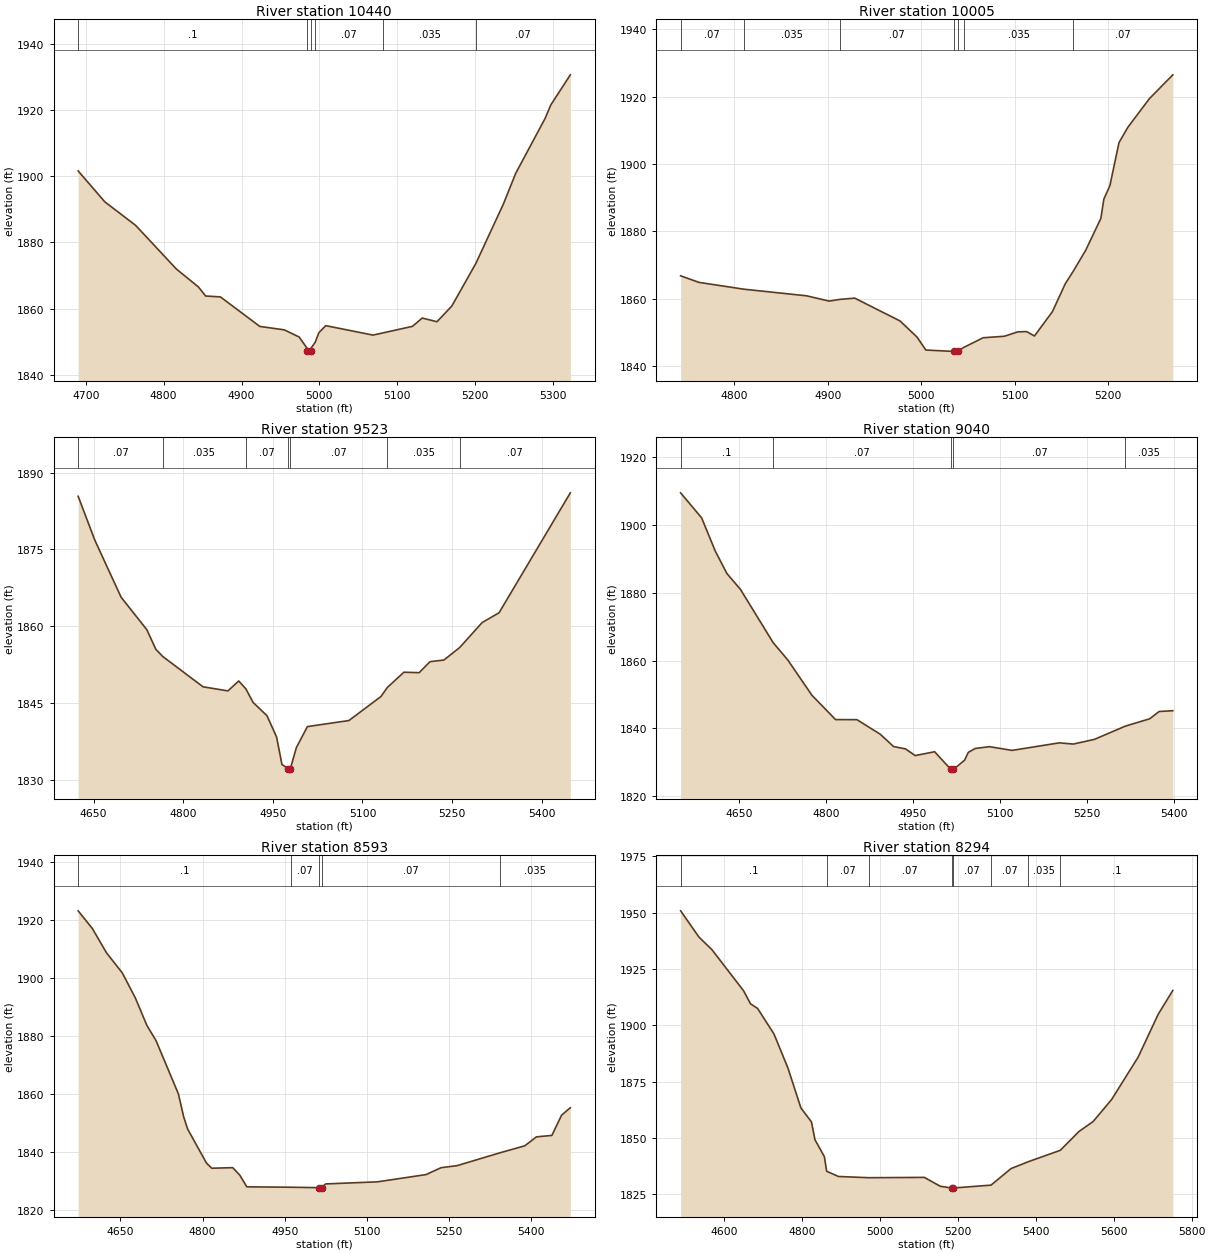
Type RM Length L Ch R = 1 ,10440   ,435,435,435
BEGIN DESCRIPTION:
Rattlesnake Creek 23.0
END DESCRIPTION:
XS GIS Cut Line= 3
      1936274.97     13947924.99        1935975.       13947825.
      1935675.03     13947924.99
#Sta/Elev= 30
  4690.1 1901.62  4724.3 1892.29    4764 1885.16  4816.2    1872  4844.7 1866.54
  4853.9 1863.82  4872.9 1863.55  4923.5 1854.63  4955.1 1853.59  4974.1 1851.42
  4984.6 1847.92  4984.7 1847.06    4985 1846.56  4988.7 1847.06  4989.3 1848.06
  4994.7 1849.85  4999.4 1852.72  5008.2 1854.86    5069 1852.01  5081.9 1852.68
  5119.6 1854.65  5132.2 1857.16  5151.2 1856.05  5170.2 1860.79  5201.1 1873.66
  5236.6 1891.68  5252.2 1900.84  5290.2 1917.54  5297.5 1921.61  5322.5 1930.66
#Mann= 6 ,-1 , 0
  4690.1      .1       0  4984.7     .05       0  4988.7      .1       0
  4994.7     .07       0  5081.9    .035       0  5201.1     .07       0
Bank Sta=4984.7,4988.7
XS Rating Curve= 0 ,0
Exp/Cntr=0.3,0.1

Type RM Length L Ch R = 1 ,10005   ,482,482,482
BEGIN DESCRIPTION:
Rattlesnake Creek 22.0
END DESCRIPTION:
XS GIS Cut Line= 3
       1936130.1     13947388.65        1935875.       13947425.
      1935625.03     13947524.99
#Sta/Elev= 30
  4742.4 1866.75  4762.1  1864.8  4810.1 1862.78  4877.3 1860.81  4901.4 1859.24
  4912.9 1859.75  4928.8 1860.12  4977.3 1853.34  4995.5 1848.55  5004.9  1844.7
  5035.2 1844.28  5035.4 1843.78  5039.2 1844.28  5045.5 1845.48  5066.3 1848.35
  5088.9 1848.79  5103.4  1850.1  5112.7 1850.18  5121.2 1848.87  5140.4  1856.1
  5154.2  1864.4  5162.9 1868.19  5176.1 1874.37  5192.3 1883.82  5195.5 1889.56
    5202  1893.6  5211.7 1906.34  5221.3 1910.93  5244.2 1919.38  5269.3 1926.48
#Mann= 7 ,-1 , 0
  4742.4     .07       0  4810.1    .035       0  4912.9     .07       0
  5035.2     .05       0  5039.2     .07       0  5045.5    .035       0
  5162.9     .07       0
Bank Sta=5035.2,5039.2
XS Rating Curve= 0 ,0
Exp/Cntr=0.3,0.1

Type RM Length L Ch R = 1 ,9523    ,483,483,483
BEGIN DESCRIPTION:
Rattlesnake Creek 21.0
END DESCRIPTION:
XS GIS Cut Line= 4
      1936248.98     13947012.08        1935875.       13946975.
      1935733.61     13947021.54      1935574.98     13947275.03
#Sta/Elev= 30
  4624.2 1885.37  4652.2 1876.77  4696.1 1865.65  4739.2  1859.3  4754.3 1855.46
  4765.7 1854.08  4833.2 1848.15  4874.9 1847.35  4892.9 1849.29  4904.8 1847.76
  4917.1 1845.08  4940.2 1842.51  4956.3 1838.35  4965.3 1832.97  4975.4 1832.18
  4975.6 1831.68  4979.4 1832.18  4989.4 1836.28  5007.9 1840.38  5077.3 1841.56
    5131 1846.26  5141.8 1848.04  5169.4    1851  5194.9 1850.91  5213.1 1853.06
  5236.3 1853.38  5262.8 1855.83  5300.3  1860.7  5328.6 1862.61  5447.9 1886.04
#Mann= 7 ,-1 , 0
  4624.2     .07       0  4765.7    .035       0  4904.8     .07       0
  4975.4     .05       0  4979.4     .07       0  5141.8    .035       0
  5262.8     .07       0
Bank Sta=4975.4,4979.4
XS Rating Curve= 0 ,0
Exp/Cntr=0.3,0.1

Type RM Length L Ch R = 1 ,9040    ,447,447,447
BEGIN DESCRIPTION:
Rattlesnake Creek 20.0
END DESCRIPTION:
XS GIS Cut Line= 3
      1936274.99       13946325.        1935875.       13946525.
      1935475.02       13946475.
#Sta/Elev= 30
  4548.5  1909.4  4584.8 1902.03  4608.4 1892.24  4628.5 1885.63  4651.9 1880.96
  4708.2 1865.32  4733.6 1860.19  4775.5 1849.75  4816.2 1842.62  4853.1  1842.6
  4893.4  1838.3  4916.4 1834.68    4937 1833.99  4953.7 1832.02  4987.3 1833.15
  5015.4 1827.94  5015.7 1827.44  5019.9 1827.94  5039.2 1830.69  5045.5 1832.96
  5057.6 1834.12  5082.2 1834.64  5121.1 1833.55  5202.8 1835.77  5226.9 1835.41
  5263.2 1836.78    5317  1840.7    5359 1842.86  5375.1    1845  5398.8 1845.23
#Mann= 5 ,-1 , 0
  4548.5      .1       0  4708.2     .07       0  5015.4     .05       0
  5019.9     .07       0    5317    .035       0
Bank Sta=5015.4,5019.9
XS Rating Curve= 0 ,0
Exp/Cntr=0.3,0.1

Type RM Length L Ch R = 1 ,8593    ,299,299,299
BEGIN DESCRIPTION:
Rattlesnake Creek 19.0
END DESCRIPTION:
XS GIS Cut Line= 3
        1936225.       13945975.        1935825.       13946125.
        1935425.       13946375.
#Sta/Elev= 30
  4572.8 1923.04  4598.9 1916.92  4624.5 1908.61  4653.4  1901.7  4677.2  1893.1
  4698.2 1883.66    4715  1878.4  4755.9 1860.06  4765.5 1852.18  4772.7 1847.99
  4807.2 1836.24  4816.8 1834.48  4855.2 1834.67  4868.1 1832.06  4880.9 1828.08
  4962.3 1827.94  5012.6 1827.79  5012.9 1827.29  5017.3 1827.79  5024.9 1829.08
  5119.6  1829.8  5208.1 1832.29  5235.7 1834.67  5264.7 1835.36  5343.3  1839.8
  5388.5 1842.19  5409.7 1845.27    5438 1845.77  5455.7 1852.74  5471.7  1855.3
#Mann= 5 ,-1 , 0
  4572.8      .1       0  4962.3     .07       0  5012.6     .05       0
  5017.3     .07       0  5343.3    .035       0
Bank Sta=5012.6,5017.3
XS Rating Curve= 0 ,0
Exp/Cntr=0.3,0.1

Type RM Length L Ch R = 1 ,8294    ,160,160,160
BEGIN DESCRIPTION:
Rattlesnake Creek 18.1
END DESCRIPTION:
XS GIS Cut Line= 4
      1936349.64     13945905.23      1935896.56     13945873.99
      1935517.66     13945989.87       1935141.4     13946160.43
#Sta/Elev= 30
  4488.1 1950.75  4535.2  1939.1  4568.4 1933.55  4649.6 1915.34  4667.6 1909.52
  4685.7 1907.47  4727.8 1896.14  4763.8 1880.96  4796.9 1863.34    4824 1857.17
    4833 1849.25  4857.1 1841.78    4863 1835.28  4893.2 1832.96  4971.1 1832.41
  5113.8 1832.56  5154.6 1828.62  5183.6 1827.85  5183.9 1827.35  5188.3 1827.85
  5284.9 1829.12  5336.5 1836.48    5381 1839.53  5462.7 1844.55  5510.6 1852.89
  5547.2 1857.35  5594.7 1867.12  5662.5 1885.84    5714 1904.85  5751.6 1915.44
#Mann= 8 ,-1 , 0
  4488.1      .1       0    4863     .07       0  4971.1     .07       0
  5183.6     .05       0  5188.3     .07       0  5284.9     .07       0
    5381    .035       0  5462.7      .1       0
Bank Sta=5183.6,5188.3
XS Rating Curve= 0 ,0
Exp/Cntr=0.3,0.1