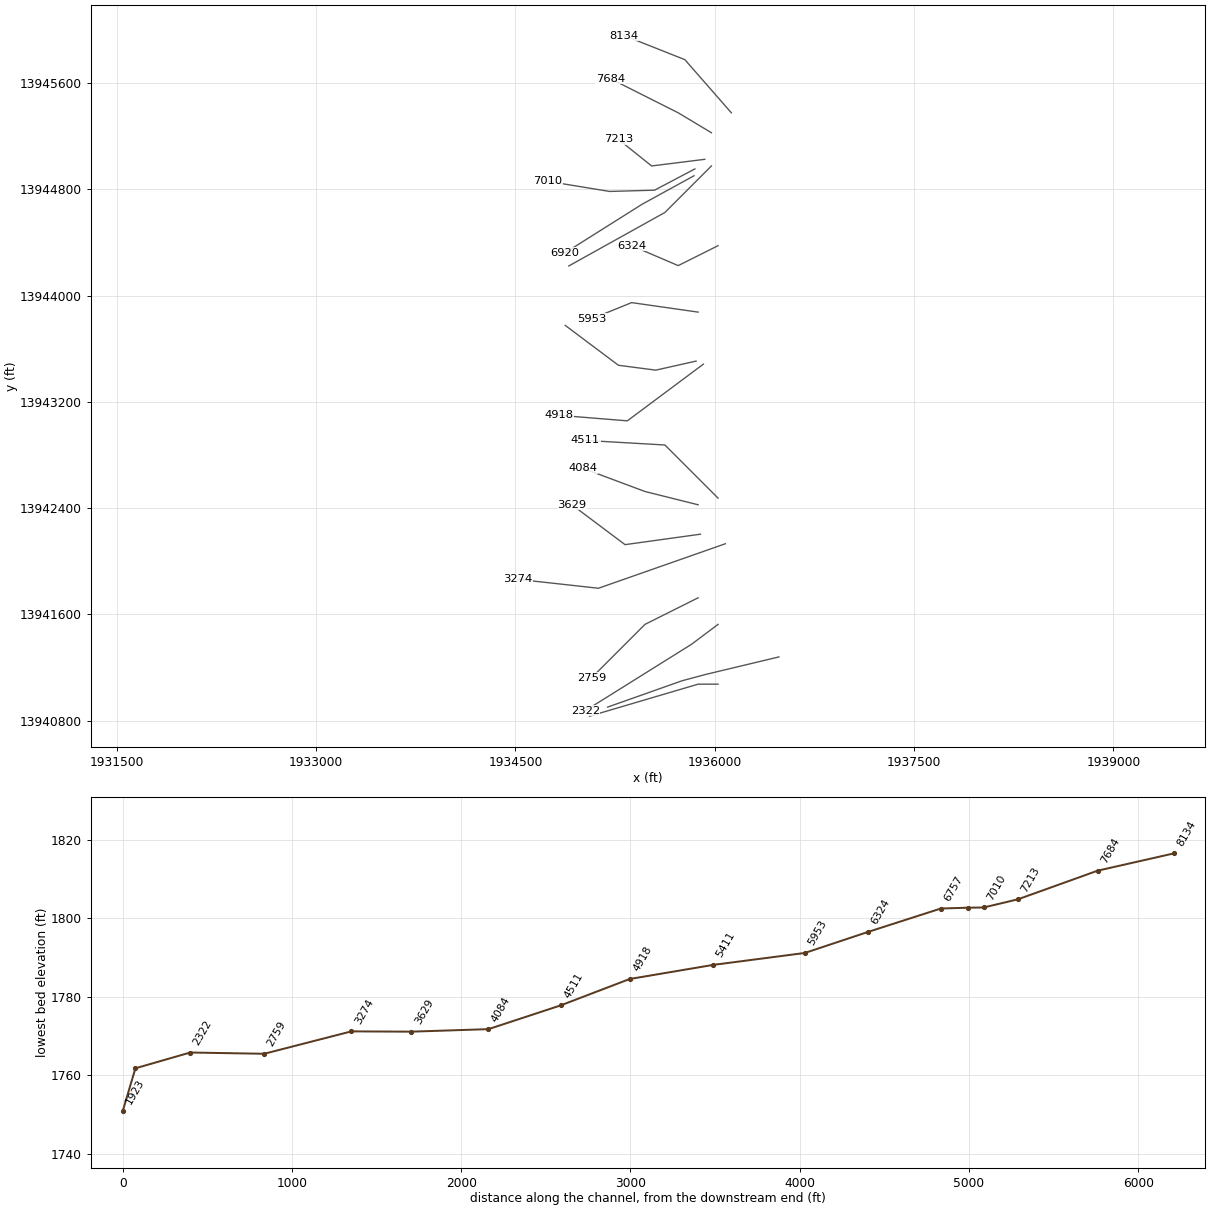
HEC-RAS study Rattlesnake Creek.prj: Rattlesnake Creek Base Level Engineering

--- Rattlesnake Creek.g01 (geometry) --- (continued)

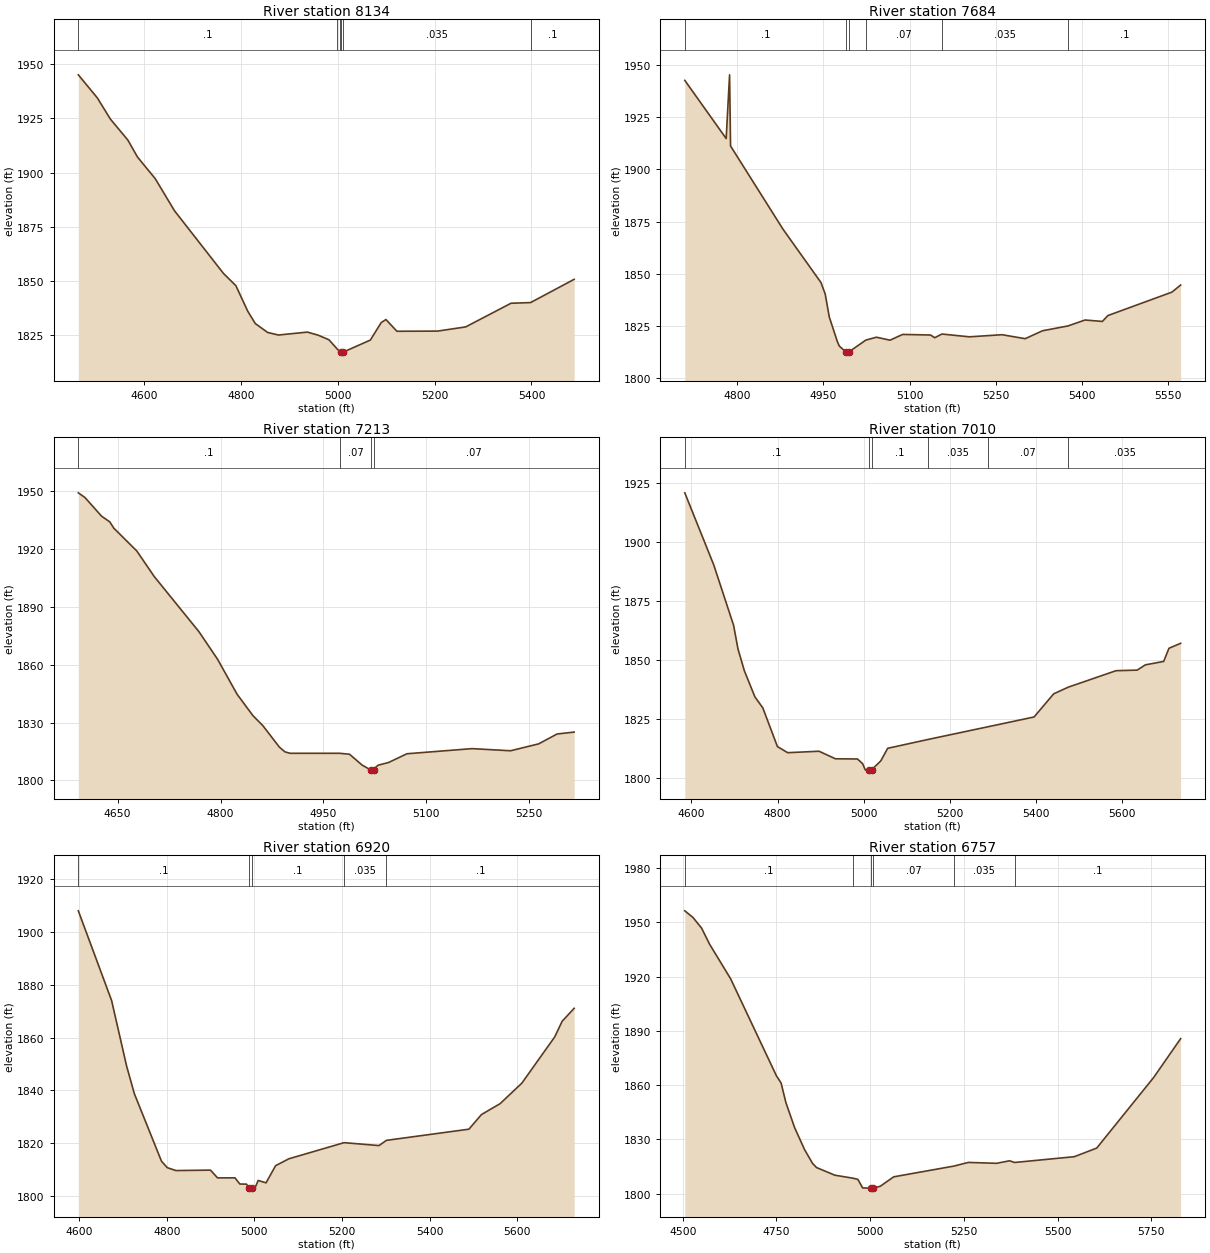
Type RM Length L Ch R = 1 ,8134    ,450,450,450
BEGIN DESCRIPTION:
Rattlesnake Creek 18.0
END DESCRIPTION:
XS GIS Cut Line= 3
      1936124.97     13945375.03        1935775.       13945775.
      1935317.38     13945956.59
#Sta/Elev= 30
  4464.3 1945.16  4503.5 1934.51  4530.6 1924.67  4566.5 1915.03  4586.4 1907.17
  4622.9 1897.22  4662.9 1882.31  4764.1  1853.3  4789.7 1847.66  4814.2 1835.84
  4829.6 1830.19  4855.2 1826.04  4877.4 1824.86  4937.2 1826.21    4960 1824.75
  4981.9 1822.66  4998.5 1818.47  5004.4 1817.15  5006.8 1816.99  5007.2 1816.49
  5011.5 1816.99  5067.3 1822.53  5089.8 1830.64  5099.5 1832.02  5122.1  1826.6
    5206 1826.67  5264.1 1828.61  5357.7 1839.55  5398.1 1839.86  5488.1 1850.61
#Mann= 6 ,-1 , 0
  4464.3      .1       0  4998.5     .07       0  5004.4    .035       0
  5006.8     .05       0  5011.5    .035       0  5398.1      .1       0
Bank Sta=5006.8,5011.5
XS Rating Curve= 0 ,0
Exp/Cntr=0.3,0.1

Type RM Length L Ch R = 1 ,7684    ,471,471,471
BEGIN DESCRIPTION:
Rattlesnake Creek 17.0
END DESCRIPTION:
XS GIS Cut Line= 3
      1935975.04     13945224.98        1935725.       13945375.
        1935215.      13945631.8
#Sta/Elev= 30
    4709 1942.61    4781 1914.77  4786.9 1945.26  4788.6 1911.21  4879.8 1871.42
    4946 1845.84  4953.3 1840.35  4960.3 1829.46  4974.3  1817.7  4977.8 1815.49
  4989.4  1812.6  4989.7  1812.1  4994.1  1812.6  5023.9 1818.33  5042.5 1819.72
    5066 1818.29    5088 1821.05  5136.6 1820.76  5143.8 1819.48  5156.4 1821.23
  5204.2  1819.9  5260.9 1820.91  5301.2 1819.01  5331.5 1822.81  5375.9 1825.12
  5405.3 1827.95  5435.5 1827.26  5445.1 1830.08  5556.4 1841.28  5571.6 1844.67
#Mann= 6 ,-1 , 0
    4709      .1       0  4989.4     .05       0  4994.1      .1       0
  5023.9     .07       0  5156.4    .035       0  5375.9      .1       0
Bank Sta=4989.4,4994.1
XS Rating Curve= 0 ,0
Exp/Cntr=0.3,0.1

Type RM Length L Ch R = 1 ,7213    ,203,203,203
BEGIN DESCRIPTION:
Rattlesnake Creek 16.0
END DESCRIPTION:
XS GIS Cut Line= 3
      1935925.04     13945025.01        1935525.       13944975.
      1935275.01     13945174.99
#Sta/Elev= 30
  4592.6 1949.31  4602.3 1946.86  4626.5  1937.2  4638.6 1934.18  4644.2 1931.02
  4677.9 1919.12  4703.3 1905.87  4768.6 1877.19  4795.8 1862.86  4824.2 1844.73
  4847.2 1833.67  4861.9 1828.38    4886 1817.23  4894.1 1814.81  4901.6 1814.06
  4973.9 1814.07  4988.2 1813.58  5006.7 1807.92  5019.7 1805.31    5020 1804.81
  5024.5 1805.31  5024.6  1806.2  5029.8 1807.87  5045.1 1809.28    5072 1813.83
  5167.1 1816.49  5223.1 1815.38  5264.1 1818.96    5291 1824.09  5315.9 1825.08
#Mann= 4 ,-1 , 0
  4592.6      .1       0  4973.9     .07       0  5019.7     .05       0
  5024.5     .07       0
Bank Sta=5019.7,5024.5
XS Rating Curve= 0 ,0
Exp/Cntr=0.3,0.1

Type RM Length L Ch R = 1 ,7010    ,90,90,90
BEGIN DESCRIPTION:
Rattlesnake Creek 15.1
END DESCRIPTION:
XS GIS Cut Line= 4
      1935850.62     13944952.76      1935547.08     13944792.63
        1935209.     13944783.18      1934745.66     13944858.96
#Sta/Elev= 30
  4584.7 1920.94    4652 1890.28    4698 1864.65  4708.1 1854.65    4723 1845.33
  4747.5 1834.24  4765.8 1829.59  4799.7 1813.15  4823.5 1810.55  4896.2 1811.17
  4934.5 1807.96  4985.5 1807.88  4997.6 1805.87  5003.6 1803.24    5013 1803.22
  5013.4 1802.72  5018.1 1803.22  5039.6 1807.06  5055.6 1812.41    5149 1816.16
  5288.6 1821.57  5395.4 1825.72    5441 1835.56  5474.8 1838.39  5585.6 1845.38
  5634.8 1845.63  5653.7 1847.86  5696.3 1849.32  5708.5  1854.9  5735.6 1857.02
#Mann= 6 ,-1 , 0
  4584.7      .1       0    5013     .05       0  5018.1      .1       0
    5149    .035       0  5288.6     .07       0  5474.8    .035       0
Bank Sta=5013,5018.1
XS Rating Curve= 0 ,0
Exp/Cntr=0.3,0.1

Type RM Length L Ch R = 1 ,6920    ,163,163,163
BEGIN DESCRIPTION:
Mapping XS dc33d4d2
END DESCRIPTION:
XS GIS Cut Line= 3
      1935844.04     13944901.19       1935454.9     13944687.74
      1934872.29     13944320.75
#Sta/Elev= 30
  4597.9 1907.91  4673.9 1873.98  4708.1 1849.26  4725.9 1838.73  4787.8 1813.24
    4801 1810.79  4820.7 1809.69  4899.7 1809.86  4915.9 1806.92  4955.7 1806.94
  4966.7  1804.6  4981.8 1804.56  4988.3 1803.17  4988.8 1802.67  4993.7 1803.17
  5002.3  1803.5  5008.7 1805.95  5026.6 1805.04  5048.4 1811.53  5078.7 1814.14
  5204.8 1820.24  5284.6 1819.14  5301.5 1821.11    5490 1825.34  5518.6 1830.87
  5561.1 1834.98  5610.8 1842.74  5685.8  1860.2  5702.9 1866.15  5730.3 1871.05
#Mann= 5 ,-1 , 0
  4597.9      .1       0  4988.3     .05       0  4993.7      .1       0
  5204.8    .035       0  5301.5      .1       0
Bank Sta=4988.3,4993.7
XS Rating Curve= 0 ,0
Exp/Cntr=0.3,0.1

Type RM Length L Ch R = 1 ,6757    ,433,433,433
BEGIN DESCRIPTION:
Rattlesnake Creek 15.0
END DESCRIPTION:
XS GIS Cut Line= 3
      1935974.99     13944974.99        1935625.       13944625.
      1934901.58     13944222.32
#Sta/Elev= 30
  4505.5 1956.41  4527.1 1952.78  4550.4 1946.82  4571.6 1937.96  4627.9 1918.78
  4749.8 1865.22  4762.5 1861.12  4775.3 1850.28  4798.6 1836.45  4825.1 1824.31
  4846.3 1816.71    4857  1814.4  4905.7 1810.18  4955.6 1808.45  4967.3 1807.84
    4980 1803.14  5001.8 1802.96  5002.3 1802.46  5007.2 1802.96  5026.6    1804
  5062.9 1809.26  5223.3  1815.2    5262 1817.23  5337.6 1816.74  5371.9 1818.14
  5385.6  1817.2  5544.9 1820.41  5604.5 1825.16  5756.5 1864.23  5828.4 1885.69
#Mann= 6 ,-1 , 0
  4505.5      .1       0  4955.6     .07       0  5001.8     .05       0
  5007.2     .07       0  5223.3    .035       0  5385.6      .1       0
Bank Sta=5001.8,5007.2
XS Rating Curve= 0 ,0
Exp/Cntr=0.3,0.1

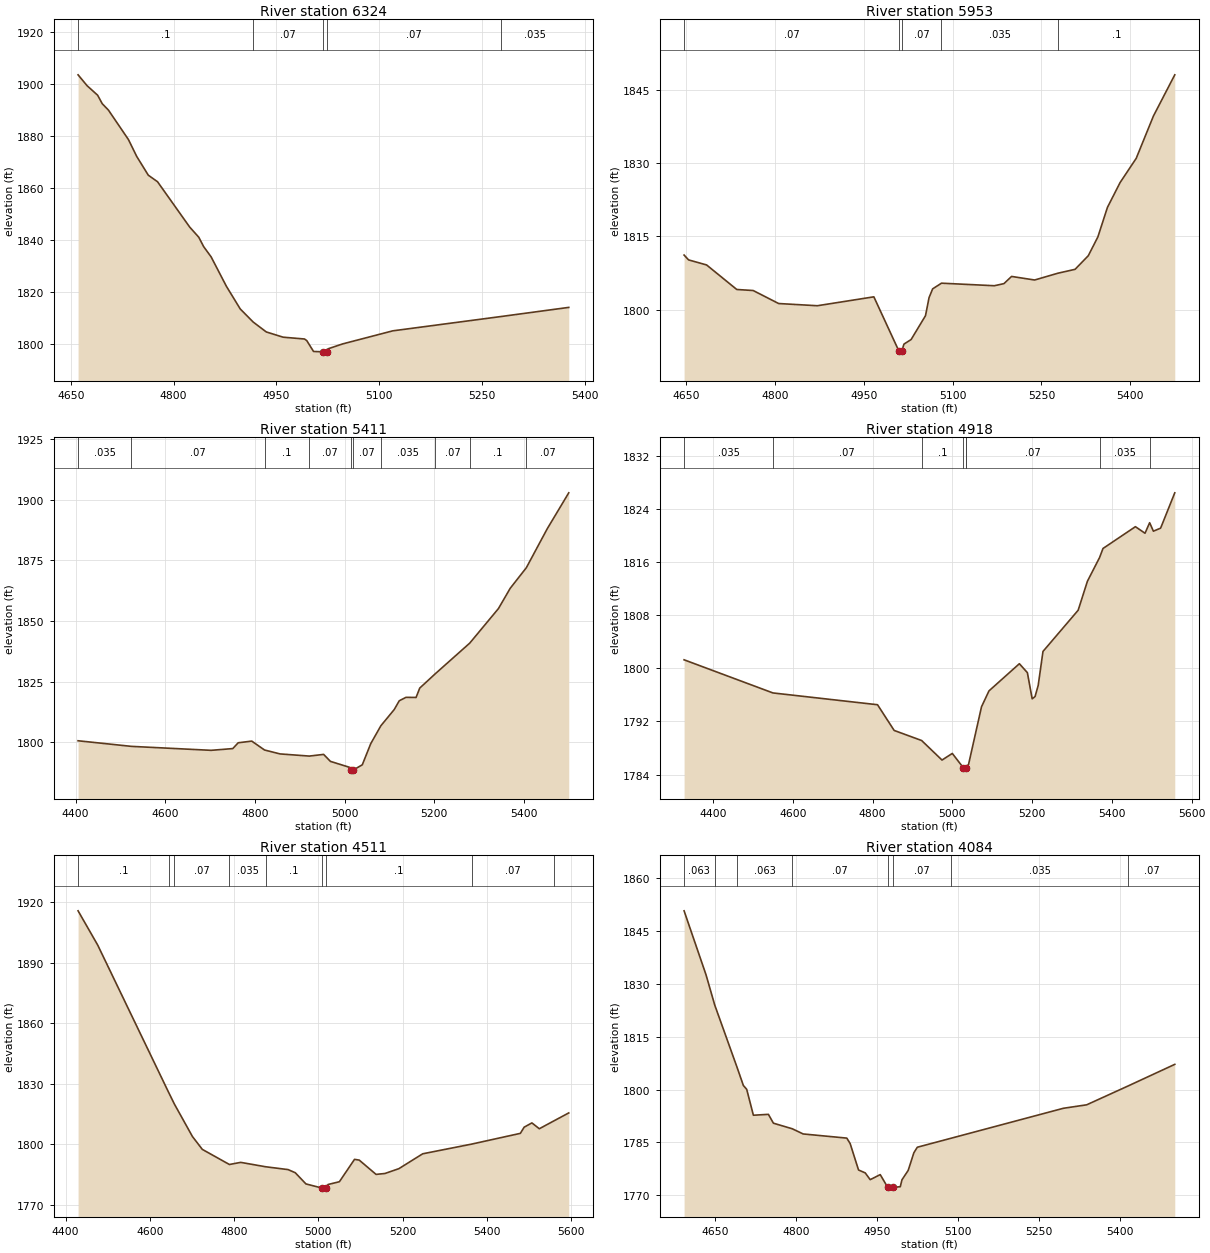
Type RM Length L Ch R = 1 ,6324    ,371,371,371
BEGIN DESCRIPTION:
Rattlesnake Creek 14.0
END DESCRIPTION:
XS GIS Cut Line= 3
      1936025.02     13944375.01        1935725.       13944225.
      1935375.02     13944374.99
#Sta/Elev= 30
  4660.5 1903.38  4673.6 1899.22  4689.1 1895.53  4695.8 1892.28  4704.9  1889.8
    4734 1878.52  4746.1 1872.03    4763 1864.82  4776.5  1862.3  4823.4  1844.9
  4836.7 1840.98  4843.8 1837.38  4854.7 1833.44  4876.9 1822.18  4897.2 1813.43
  4916.1  1808.4  4935.2  1804.6  4959.8 1802.58    4991 1801.89  4994.3 1801.27
  5004.2  1797.1  5017.8 1796.96  5018.2 1796.46  5023.2 1796.96  5023.6 1797.75
  5026.1 1798.18  5046.4 1799.98  5119.8 1805.02  5277.8 1810.52  5376.7 1814.03
#Mann= 5 ,-1 , 0
  4660.5      .1       0  4916.1     .07       0  5017.8     .05       0
  5023.2     .07       0  5277.8    .035       0
Bank Sta=5017.8,5023.2
XS Rating Curve= 0 ,0
Exp/Cntr=0.3,0.1

Type RM Length L Ch R = 1 ,5953    ,542,542,542
BEGIN DESCRIPTION:
Rattlesnake Creek 13.0
END DESCRIPTION:
XS GIS Cut Line= 3
      1935875.01       13943875.      1935374.32     13943946.47
      1935075.09     13943825.04
#Sta/Elev= 30
  4646.4 1811.19    4654  1810.2  4684.4 1809.17  4735.4 1804.15  4763.1 1803.94
  4806.1 1801.28  4871.5 1800.83  4966.9 1802.65  5008.9 1791.64  5009.3 1791.14
  5014.3 1791.64  5017.7 1792.98  5029.8 1793.92  5054.1 1798.79  5060.1 1802.48
  5066.2 1804.28  5081.1 1805.44  5170.4 1804.92  5186.6 1805.35  5199.5 1806.82
  5238.4 1806.09  5277.8 1807.48  5306.7 1808.27    5329 1811.05  5345.2 1814.89
  5361.4 1820.94  5382.7    1826    5410 1830.97  5439.1 1839.63  5475.1 1848.04
#Mann= 5 ,-1 , 0
  4646.4     .07       0  5008.9     .05       0  5014.3     .07       0
  5081.1    .035       0  5277.8      .1       0
Bank Sta=5008.9,5014.3
XS Rating Curve= 0 ,0
Exp/Cntr=0.3,0.1

Type RM Length L Ch R = 1 ,5411    ,493,493,493
BEGIN DESCRIPTION:
Rattlesnake Creek 12.0
END DESCRIPTION:
XS GIS Cut Line= 4
      1935859.63     13943506.49      1935556.07     13943438.25
        1935275.       13943475.        1934875.       13943775.
#Sta/Elev= 30
  4405.4 1800.61  4524.4  1798.3  4702.2 1796.67  4750.5 1797.39  4762.6 1799.78
  4792.8 1800.47  4821.4  1796.8    4856 1795.19  4921.2  1794.3  4953.2 1794.99
  4968.3 1792.12  5011.1 1789.66  5014.2  1788.6  5014.6  1788.1  5019.7  1788.6
  5039.4  1790.7  5058.2 1799.39  5080.8 1806.78  5110.7 1813.48  5121.9 1817.09
  5136.9  1818.5  5159.4 1818.46  5167.6 1822.32  5202.5 1828.26  5279.1 1840.84
  5343.2 1855.09  5369.4 1863.43  5405.4 1871.92  5451.9 1887.93    5500 1902.77
#Mann= 10 ,-1 , 0
  4405.4    .035       0  4524.4     .07       0  4821.4      .1       0
  4921.2     .07       0  5014.2     .05       0  5019.7     .07       0
  5080.8    .035       0  5202.5     .07       0  5279.1      .1       0
  5405.4     .07       0
Bank Sta=5014.2,5019.7
XS Rating Curve= 0 ,0
Exp/Cntr=0.3,0.1

Type RM Length L Ch R = 1 ,4918    ,407,407,407
BEGIN DESCRIPTION:
Rattlesnake Creek 11.0
END DESCRIPTION:
XS GIS Cut Line= 3
      1935914.33     13943483.35      1935342.24     13943056.78
      1934827.04     13943098.49
#Sta/Elev= 30
  4327.2 1801.31    4550 1796.31  4812.3 1794.53    4854 1790.65  4922.9 1789.13
    4974 1786.18  4999.8 1787.18  5027.6 1785.01    5028 1784.51  5033.2 1785.01
  5033.3 1785.01  5040.6 1785.53  5073.1 1794.23  5091.8 1796.62    5168 1800.72
  5188.1 1799.37  5200.1 1795.42  5207.3 1795.76  5215.2 1797.44  5227.2 1802.57
  5315.4 1808.79  5338.6 1813.16  5369.1 1816.74  5377.7 1818.11    5459  1821.4
  5483.1 1820.41  5494.7    1822  5504.1 1820.72  5522.2 1821.18  5557.7 1826.51
#Mann= 8 ,-1 , 0
  4327.2    .035       0    4550     .07       0  4922.9      .1       0
  5027.6     .05       0  5033.2      .1       0  5033.3     .07       0
  5369.1    .035       0  5494.7     .07       0
Bank Sta=5027.6,5033.2
XS Rating Curve= 0 ,0
Exp/Cntr=0.3,0.1

Type RM Length L Ch R = 1 ,4511    ,427,427,427
BEGIN DESCRIPTION:
Rattlesnake Creek 10.0
END DESCRIPTION:
XS GIS Cut Line= 3
      1936025.01     13942474.99        1935625.       13942875.
      1935026.69     13942909.41
#Sta/Elev= 30
  4429.7 1915.62  4476.4 1898.63    4645 1825.59  4658.6 1819.84  4701.3 1803.83
  4724.7 1797.48    4789    1790  4815.8 1791.05  4875.2 1788.87  4928.3 1787.47
  4945.3 1785.93  4970.7 1780.38  5009.4  1778.3  5009.9  1777.8  5018.6  1778.3
    5023 1780.08  5050.1 1781.46  5086.1 1792.55  5097.3 1792.17  5137.2  1785.1
  5158.2 1785.54  5191.3 1787.93  5247.9 1795.29  5363.8 1800.08  5479.8 1805.42
  5488.8 1808.48  5507.2 1810.59  5524.8  1807.7  5558.7 1811.51  5594.7 1815.54
#Mann= 9 ,-1 , 0
  4429.7      .1       0    4645    .063       0  4658.6     .07       0
    4789    .035       0  4875.2      .1       0  5009.4     .05       0
  5018.6      .1       0  5363.8     .07       0  5558.7    .035       0
Bank Sta=5009.4,5018.6
XS Rating Curve= 0 ,0
Exp/Cntr=0.3,0.1

Type RM Length L Ch R = 1 ,4084    ,455,455,455
BEGIN DESCRIPTION:
Rattlesnake Creek 9.0
END DESCRIPTION:
XS GIS Cut Line= 3
      1935874.98     13942425.01        1935475.       13942525.
      1935009.53     13942698.65
#Sta/Elev= 30
  4591.9  1850.8  4632.5 1832.65  4648.7 1824.03  4689.9 1806.41  4701.7  1801.2
  4707.9  1800.1  4720.3 1792.74  4748.1 1792.99  4757.4 1790.48  4792.4 1788.89
  4812.5 1787.42  4893.4 1786.24  4899.6 1784.68  4915.1 1777.19  4927.5 1776.36
  4936.7 1774.44  4955.3 1775.87  4969.2 1772.25  4969.7 1771.75  4978.4 1772.25
  4992.4 1772.43  4995.6 1774.41  5007.1 1777.07  5017.6 1782.08    5024 1783.65
  5087.2 1786.23  5294.5 1794.71  5337.8  1795.7  5414.5 1801.05    5501 1807.19
#Mann= 8 ,-1 , 0
  4591.9    .063       0  4648.7    .094       0  4689.9    .063       0
  4792.4     .07       0  4969.2     .05       0  4978.4     .07       0
  5087.2    .035       0  5414.5     .07       0
Bank Sta=4969.2,4978.4
XS Rating Curve= 0 ,0
Exp/Cntr=0.3,0.1

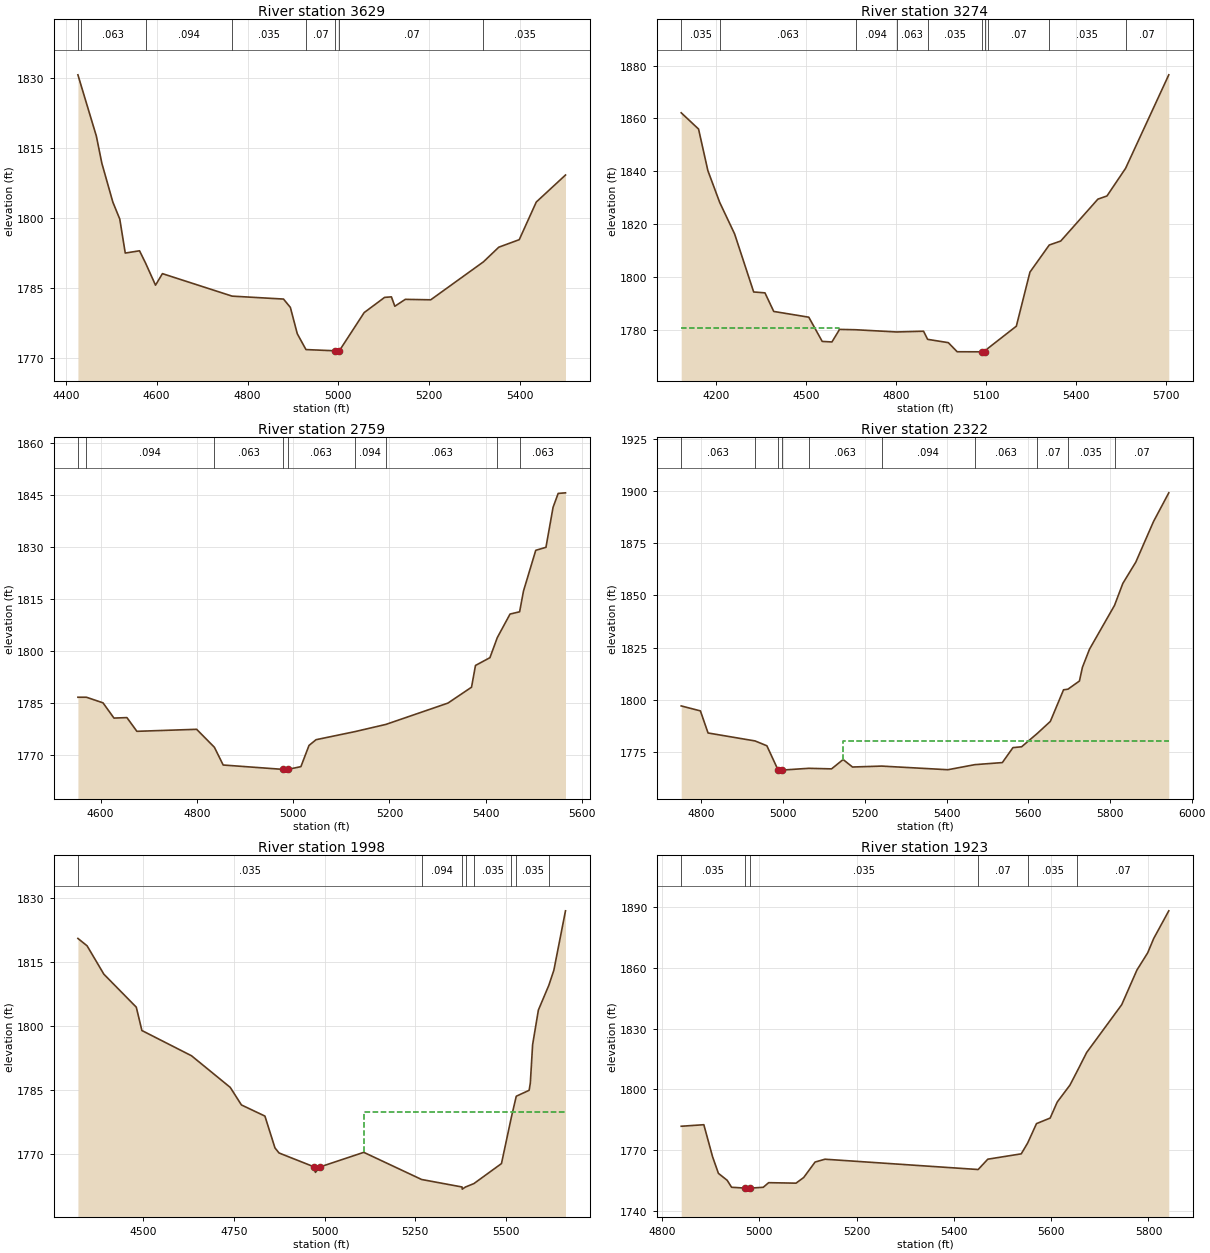
Type RM Length L Ch R = 1 ,3629    ,355,355,355
BEGIN DESCRIPTION:
Rattlesnake Creek 8.0
END DESCRIPTION:
XS GIS Cut Line= 3
      1935892.63     13942203.74        1935325.       13942125.
      1934924.97     13942425.02
#Sta/Elev= 30
  4426.7 1830.77  4433.1 1828.69  4467.3 1817.63  4479.4  1811.8  4503.6 1803.48
  4518.8 1799.85  4530.9 1792.56  4562.3 1793.05  4575.5 1790.43  4597.5 1785.68
  4612.7 1788.15    4766 1783.33  4879.2  1782.7  4894.3 1780.91  4909.5 1775.27
  4928.6 1771.87  4992.7 1771.61  4993.2 1771.11    5002 1771.61  5056.7  1779.8
  5101.7 1783.06  5116.7 1783.17  5124.2 1781.16  5147.3 1782.64  5203.2 1782.54
  5319.2 1790.68    5353 1793.82    5398 1795.43  5435.5  1803.5  5499.8 1809.29
#Mann= 8 ,-1 , 0
  4426.7      .1       0  4433.1    .063       0  4575.5    .094       0
    4766    .035       0  4928.6     .07       0  4992.7     .05       0
    5002     .07       0  5319.2    .035       0
Bank Sta=4992.7,5002
XS Rating Curve= 0 ,0
Exp/Cntr=0.3,0.1

Type RM Length L Ch R = 1 ,3274    ,515,515,515
BEGIN DESCRIPTION:
Rattlesnake Creek 7.0
END DESCRIPTION:
XS GIS Cut Line= 3
      1936080.25     13942131.84      1935124.68     13941796.86
      1934516.75     13941863.95
#Sta/Elev= 30
  4084.6 1862.15  4142.4    1856  4173.4 1840.27  4212.8 1828.24  4262.4 1816.33
    4326 1794.33  4363.6 1793.99  4392.8 1786.96  4509.6 1784.78  4554.3 1775.61
  4586.7 1775.41  4612.1 1780.16  4666.1 1780.03  4802.1 1779.19  4891.9 1779.47
  4905.4  1776.4  4974.5 1775.14  5003.9  1771.7  5086.3 1771.68  5086.8 1771.18
  5095.6 1771.68  5106.6 1773.01    5201 1781.38  5246.3 1801.84  5310.6  1812.1
  5348.9 1813.61  5472.7 1829.47  5502.9 1830.67  5564.9 1841.13  5708.8 1876.52
#Mann= 10 ,-1 , 0
  4084.6    .035       0  4212.8    .063       0  4666.1    .094       0
  4802.1    .063       0  4905.4    .035       0  5086.3    .035       0
  5095.6    .035       0  5106.6     .07       0  5310.6    .035       0
  5564.9     .07       0
#XS Ineff= 2 , 0
         4611.44 1780.84
Permanent Ineff=
       F       F
Bank Sta=5086.3,5095.6
XS Rating Curve= 0 ,0
Exp/Cntr=0.3,0.1

Type RM Length L Ch R = 1 ,2759    ,437,437,437
BEGIN DESCRIPTION:
Rattlesnake Creek 6.0
END DESCRIPTION:
XS GIS Cut Line= 3
      1935875.01     13941725.01        1935475.       13941525.
      1935075.01     13941125.01
#Sta/Elev= 30
  4552.8 1786.75  4570.5 1786.75  4604.9 1785.14  4627.7 1780.75  4654.6 1780.89
  4675.3 1776.94  4799.4 1777.52  4836.3 1772.35  4854.6 1767.24  4979.2 1765.98
  4979.7 1765.48  4988.6 1765.98    5016 1766.77  5032.9 1772.88  5047.5 1774.53
  5128.2 1776.85  5192.6 1778.93  5321.4 1785.06  5370.5 1789.64  5378.7  1795.9
  5408.7 1798.14  5424.1 1803.94  5450.5  1810.7  5470.4 1811.35  5478.4 1817.31
  5503.9 1829.05  5525.1 1829.91  5539.9 1841.44  5550.5 1845.43  5565.7  1845.6
#Mann= 9 ,-1 , 0
  4552.8    .063       0  4570.5    .094       0  4836.3    .063       0
  4979.2     .05       0  4988.6    .063       0  5128.2    .094       0
  5192.6    .063       0  5424.1     .07       0  5470.4    .063       0
Bank Sta=4979.2,4988.6
XS Rating Curve= 0 ,0
Exp/Cntr=0.3,0.1

Type RM Length L Ch R = 1 ,2322    ,324,324,324
BEGIN DESCRIPTION:
Rattlesnake Creek 5.0
END DESCRIPTION:
XS GIS Cut Line= 3
      1936025.02     13941525.02        1935825.       13941375.
      1935025.02     13940875.01
#Sta/Elev= 30
  4750.6 1797.03  4797.6 1794.65  4816.3 1784.07  4931.4 1780.26  4960.3 1777.94
  4987.8  1766.3  4988.3  1765.8  4997.3  1766.3  5062.8 1767.15  5118.6 1766.88
  5146.9 1771.35  5169.9 1767.77  5241.2 1768.21  5403.4 1766.47  5469.2  1768.9
  5536.6 1769.89  5562.6 1777.06  5583.8 1777.46  5622.6 1783.93  5654.1 1789.61
  5686.4 1804.75  5697.2 1805.05  5725.3 1808.96  5732.6  1815.5  5749.9 1824.18
  5811.2 1845.19  5831.5  1855.7  5863.3 1865.92  5906.7 1885.38    5944  1899.1
#Mann= 10 ,-1 , 0
  4750.6    .063       0  4931.4    .035       0  4987.8    .035       0
  4997.3    .035       0  5062.8    .063       0  5241.2    .094       0
  5469.2    .063       0  5622.6     .07       0  5697.2    .035       0
  5811.2     .07       0
#XS Ineff= 2 , 0
                         5146.19         1780.26
Permanent Ineff=
       F       F
Bank Sta=4987.8,4997.3
XS Rating Curve= 0 ,0
Exp/Cntr=0.3,0.1

Type RM Length L Ch R = 1 ,1998    ,75,75,75
BEGIN DESCRIPTION:
Rattlesnake Creek 4.1
END DESCRIPTION:
XS GIS Cut Line= 4
      1936483.04     13941280.14      1935928.38     13941147.34
       1935753.9     13941100.46      1935193.96     13940902.53
#Sta/Elev= 30
  4319.6 1820.53  4344.9  1818.8  4391.2 1812.15  4480.6 1804.42  4496.1 1798.95
    4633 1793.03  4739.8 1785.62  4770.6 1781.51  4835.4  1778.9  4863.1 1771.44
  4874.4 1770.25 4969.82 1767.04 4974.77 1765.71 4987.14 1766.98  5108.1  1770.4
  5267.6 1764.04  5379.2 1762.28  5379.7 1761.78  5388.7 1762.28  5411.9 1763.08
  5487.9 1767.77  5515.3 1778.67  5528.7 1783.55  5564.2 1784.94  5567.5 1786.64
  5573.8 1795.63  5589.7 1803.74  5618.7 1809.58  5632.4 1813.08  5664.5    1827
#Mann= 8 ,-1 , 0
  4319.6    .035       0  5267.6    .094       0  5379.2    .035       0
  5388.7    .094       0  5411.9    .035       0  5515.3     .07       0
  5528.7    .035       0  5618.7     .07       0
#XS Ineff= 2 , 0
                         5107.62         1779.89
Permanent Ineff=
       F       F
#Block Obstruct= 2 , 0
                         5197.31         1765.89
Bank Sta=4969.82,4987.14
XS Rating Curve= 0 ,0
Exp/Cntr=0.3,0.1

Type RM Length L Ch R = 1 ,1923    ,501,501,501
BEGIN DESCRIPTION:
Rattlesnake Creek 4.0
END DESCRIPTION:
XS GIS Cut Line= 3
      1936024.96       13941075.        1935875.       13941075.
      1935057.65     13940834.01
#Sta/Elev= 30
  4839.6 1781.83  4886.1 1782.59  4904.1 1766.78  4916.1 1758.61  4934.1  1755.2
  4943.1 1751.77  4971.4 1751.35  4971.9 1750.85  4980.9 1751.35  5008.2 1751.75
  5019.3 1754.03  5075.6 1753.79  5091.3 1756.57  5114.8  1764.2  5135.1 1765.59
  5449.9 1760.51  5469.7  1765.6  5538.5 1768.24  5551.8 1773.64  5569.8 1783.13
  5597.9 1785.87  5612.4 1793.75  5638.6 1802.12  5653.6 1809.06    5673 1818.21
    5745 1841.75  5776.2  1858.8  5798.4 1867.31  5810.6 1874.31  5841.7 1887.99
#Mann= 6 ,-1 , 0
  4839.6    .035       0  4971.4    .035       0  4980.9    .035       0
  5449.9     .07       0  5551.8    .035       0  5653.6     .07       0
#XS Ineff= 2 , 0
                         5137.67         1765.26
Permanent Ineff=
       F       F
Bank Sta=4971.4,4980.9
XS Rating Curve= 0 ,0
Exp/Cntr=0.3,0.1