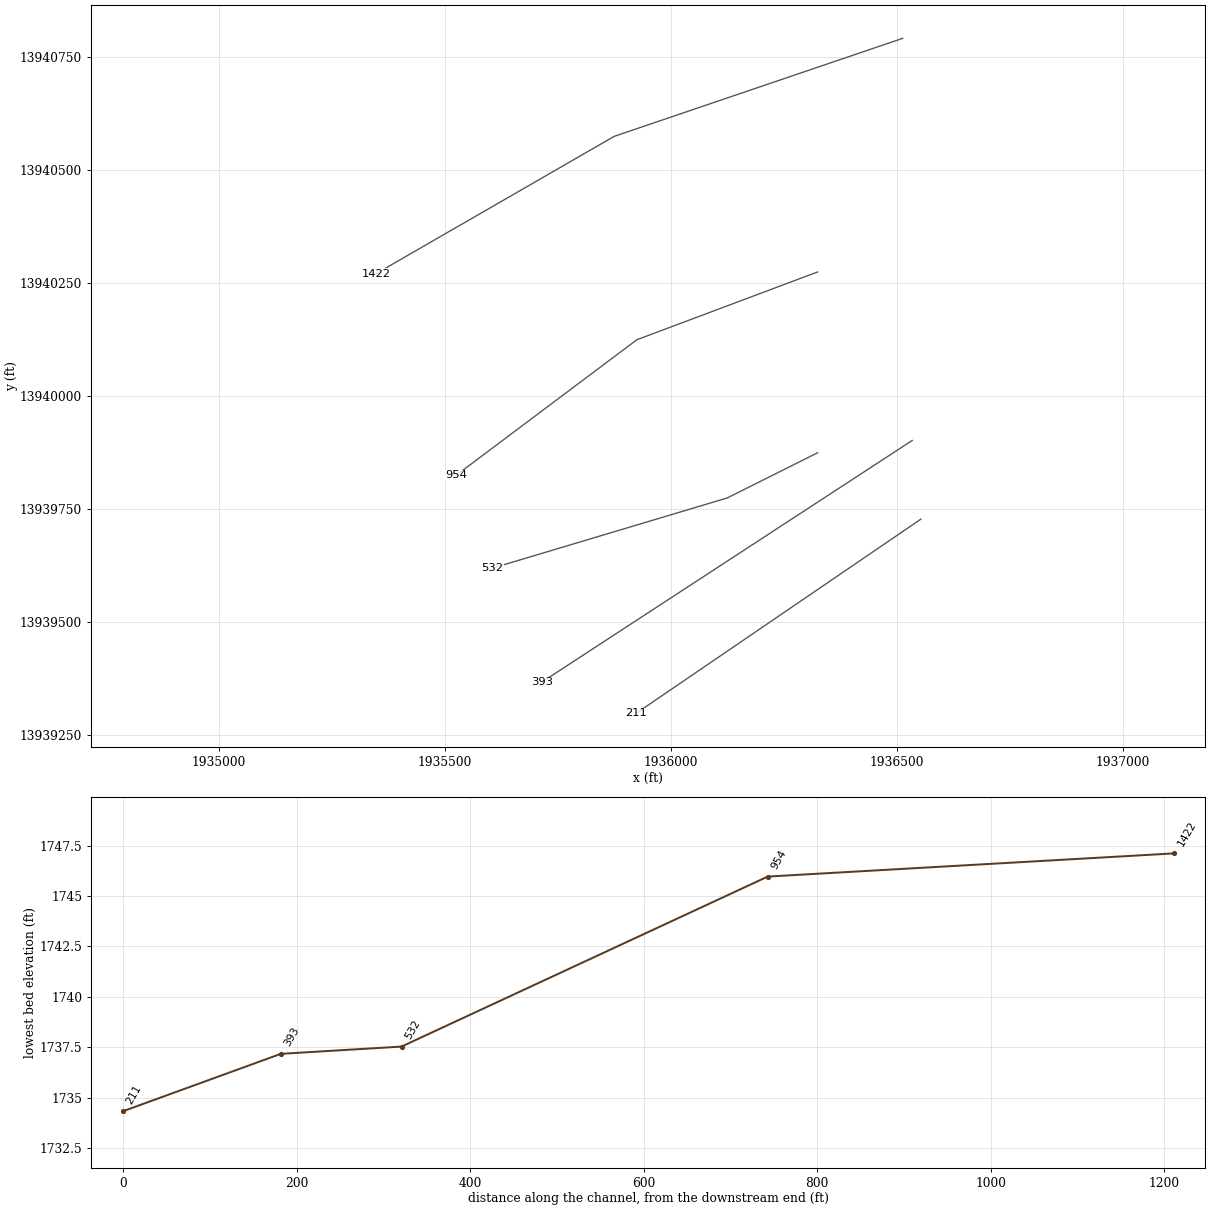
HEC-RAS study Rattlesnake Creek.prj: Rattlesnake Creek Base Level Engineering

--- Rattlesnake Creek.g01 (geometry) --- (continued)

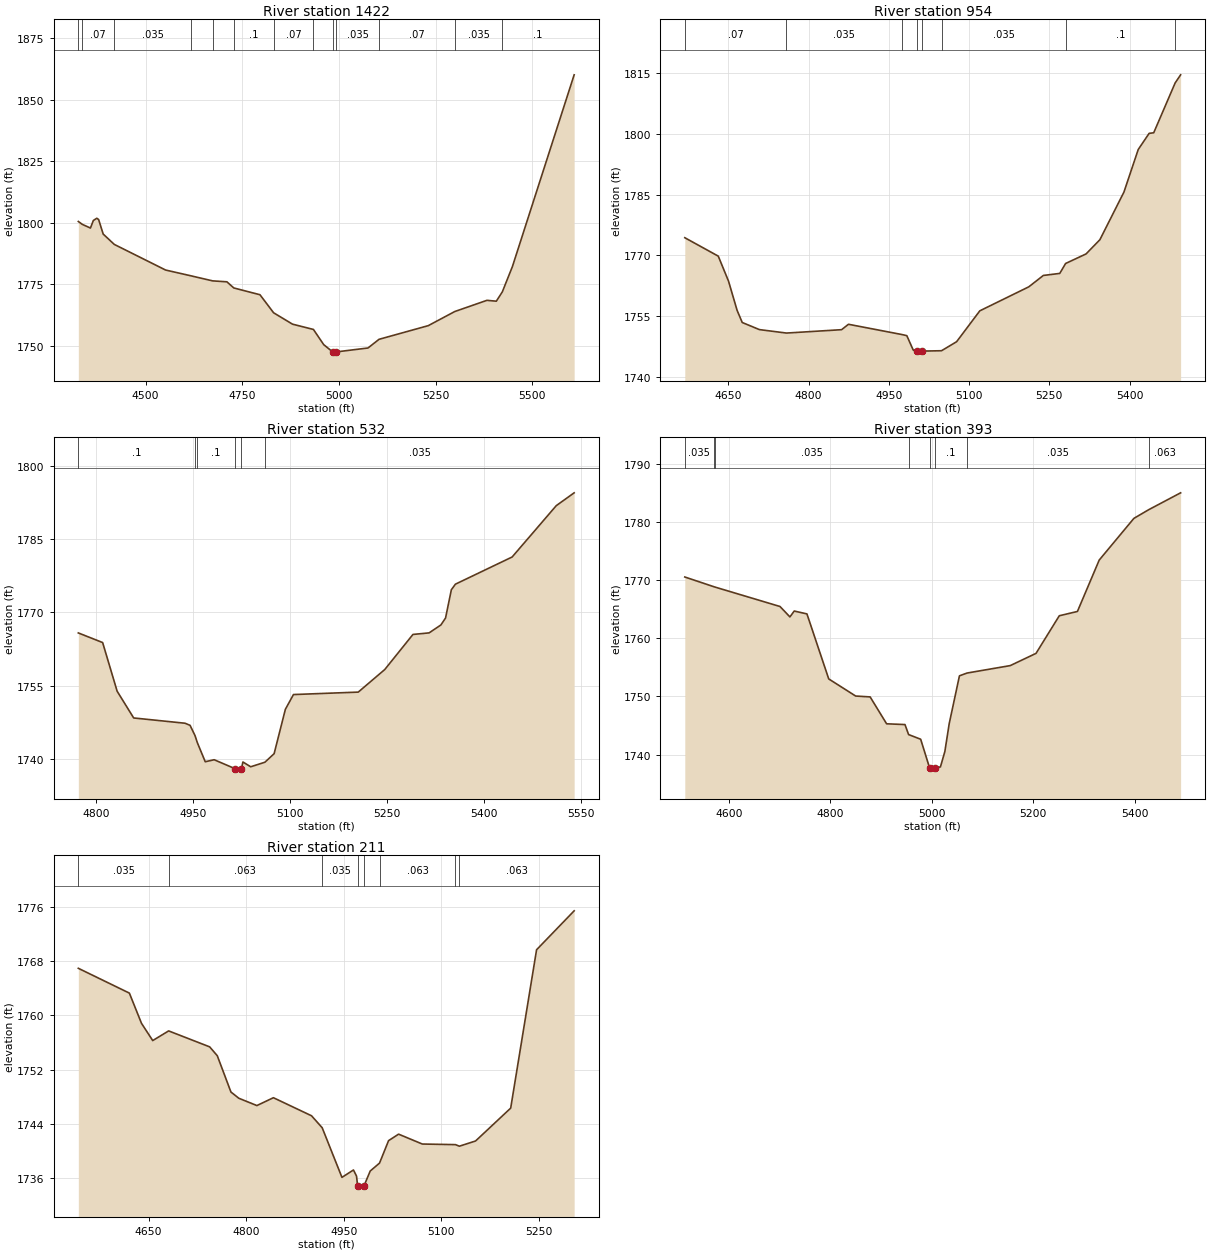
Type RM Length L Ch R = 1 ,1422    ,468,468,468
BEGIN DESCRIPTION:
Rattlesnake Creek 3.0
END DESCRIPTION:
XS GIS Cut Line= 3
      1936513.28     13940791.84        1935875.       13940575.
        1935348.      13940271.2
#Sta/Elev= 30
  4325.9 1800.58  4336.1 1799.42  4357.2 1797.92  4364.8 1800.99  4373.7 1801.89
  4378.4 1801.38  4390.2 1795.47  4418.9 1791.27  4551.7 1780.86  4617.9 1778.49
  4673.3 1776.46  4710.2 1776.08    4728 1773.59  4795.7 1770.83    4831  1763.5
  4879.8 1758.89    4934 1756.73  4960.5 1750.58  4983.7 1747.62  4984.2 1747.12
  4993.4 1747.62  5075.1 1749.21  5103.7 1752.73    5231 1758.28  5299.5 1764.01
  5382.7 1768.56    5407 1768.21  5422.5 1771.99  5448.5 1782.22  5608.3 1860.14
#Mann= 13 ,-1 , 0
  4325.9    .035       0  4336.1     .07       0  4418.9    .035       0
  4617.9     .07       0  4673.3    .035       0    4728      .1       0
    4831     .07       0    4934    .035       0  4983.7    .035       0
  4993.4    .035       0  5103.7     .07       0  5299.5    .035       0
  5422.5      .1       0
Bank Sta=4983.7,4993.4
XS Rating Curve= 0 ,0
Exp/Cntr=0.3,0.1

Type RM Length L Ch R = 1 ,954     ,422,422,422
BEGIN DESCRIPTION:
Rattlesnake Creek 2.0
END DESCRIPTION:
XS GIS Cut Line= 3
      1936325.02     13940275.01        1935925.       13940125.
      1935525.01     13939825.01
#Sta/Elev= 30
  4568.4 1774.38    4631 1769.84  4650.2 1763.68  4666.2 1756.51  4675.8 1753.51
  4707.9 1751.76  4758.5 1750.91  4861.6 1751.74  4874.5 1753.07  4974.2 1750.55
  4983.6 1750.27  4995.6 1746.72  5002.7 1746.47  5003.2 1745.97  5012.5 1746.47
  5048.5 1746.56  5076.7 1748.78  5120.1 1756.38  5211.7 1762.29  5238.9 1765.09
  5269.6 1765.59  5280.5 1768.03  5318.8 1770.39  5344.6 1773.88  5389.6 1785.61
  5416.3 1796.08  5436.7 1800.06  5445.3 1800.21  5485.4 1812.48  5495.6 1814.47
#Mann= 8 ,-1 , 0
  4568.4     .07       0  4758.5    .035       0  4974.2     .07       0
  5002.7     .05       0  5012.5     .07       0  5048.5    .035       0
  5280.5      .1       0  5485.4    .035       0
Bank Sta=5002.7,5012.5
XS Rating Curve= 0 ,0
Exp/Cntr=0.3,0.1

Type RM Length L Ch R = 1 ,532     ,139,139,139
BEGIN DESCRIPTION:
Rattlesnake Creek 1.0
END DESCRIPTION:
XS GIS Cut Line= 3
      1936324.98     13939874.99        1936125.       13939775.
      1935604.54     13939619.42
#Sta/Elev= 30
  4772.3 1765.81  4809.9 1763.84  4832.3 1753.89  4857.9 1748.41  4937.4 1747.33
  4945.1  1746.9  4952.7 1744.82  4956.4 1743.34  4968.6 1739.45  4982.4 1739.86
  5014.7 1738.03  5015.2 1737.53  5024.6 1738.03  5026.8  1739.4  5038.9 1738.42
  5060.8 1739.35  5075.1  1741.1  5092.5 1750.18    5105  1753.2  5205.2  1753.7
  5246.2 1758.32  5289.8  1765.5  5314.8 1765.82    5333 1767.44  5340.2 1768.86
  5349.2 1774.65  5355.5 1775.79  5443.2 1781.35  5511.4 1791.85  5539.1 1794.48
#Mann= 6 ,-1 , 0
  4772.3      .1       0  4952.7    .035       0  4956.4      .1       0
  5014.7     .05       0  5024.6      .1       0  5060.8    .035       0
Bank Sta=5014.7,5024.6
XS Rating Curve= 0 ,0
Exp/Cntr=0.3,0.1

Type RM Length L Ch R = 1 ,393     ,182,182,182
BEGIN DESCRIPTION:
Mapping XS b4982c28
END DESCRIPTION:
XS GIS Cut Line= 2
      1936534.28     13939902.24      1935714.96     13939367.65
#Sta/Elev= 30
  4512.7 1770.52  4570.4 1768.84  4571.5 1768.81  4700.6 1765.45  4720.1 1763.66
  4728.6 1764.67  4753.7 1764.18  4796.7 1753.01  4849.8 1750.07  4878.4 1749.92
  4910.9  1745.3  4947.1 1745.17  4954.3 1743.45  4978.1 1742.65  4995.9 1737.67
  4996.4 1737.17  5005.8 1737.67  5017.1  1737.9  5025.8 1740.53  5034.4 1745.32
  5054.6 1753.54  5069.6 1754.02  5154.9  1755.3  5205.7  1757.4  5251.6 1763.86
  5287.4  1764.6  5330.4 1773.43  5398.8 1780.59    5428 1782.08    5491 1784.98
#Mann= 8 ,-1 , 0
  4512.7    .035       0  4570.4     .07       0  4571.5    .035       0
  4954.3      .1       0  4995.9     .05       0  5005.8      .1       0
  5069.6    .035       0    5428    .063       0
Bank Sta=4995.9,5005.8
XS Rating Curve= 0 ,0
Exp/Cntr=0.3,0.1

Type RM Length L Ch R = 1 ,211     ,0,0,0
BEGIN DESCRIPTION:
Rattlesnake Creek 0.0
END DESCRIPTION:
XS GIS Cut Line= 2
      1936553.33     13939728.07      1935923.38     13939298.45
#Sta/Elev= 30
    4542 1766.98  4620.5 1763.31  4639.1 1758.85  4656.4 1756.29  4680.9 1757.72
    4744 1755.36  4755.7 1754.05  4776.7 1748.68  4788.8 1747.76  4816.6 1746.68
    4842 1747.84  4900.6 1745.17    4917  1743.4  4947.4 1736.06  4965.1 1737.15
  4969.8 1736.25  4971.5 1734.82    4972 1734.32  4981.4 1734.82  4990.9    1737
  5005.2 1738.17  5019.1 1741.49  5034.5 1742.45    5071 1740.99    5122  1740.9
    5128 1740.67  5152.9 1741.44  5206.9  1746.3  5246.7 1769.72  5304.5 1775.48
#Mann= 8 ,-1 , 0
    4542    .035       0  4680.9    .063       0    4917    .035       0
  4971.5    .035       0  4981.4    .035       0  5005.2    .063       0
    5122    .035       0    5128    .063       0
Bank Sta=4971.5,4981.4
XS Rating Curve= 0 ,0
Exp/Cntr=0.3,0.1

Chan Stop Cuts=-1
Use User Specified Reach Order=0
Composite Channel Slope=5