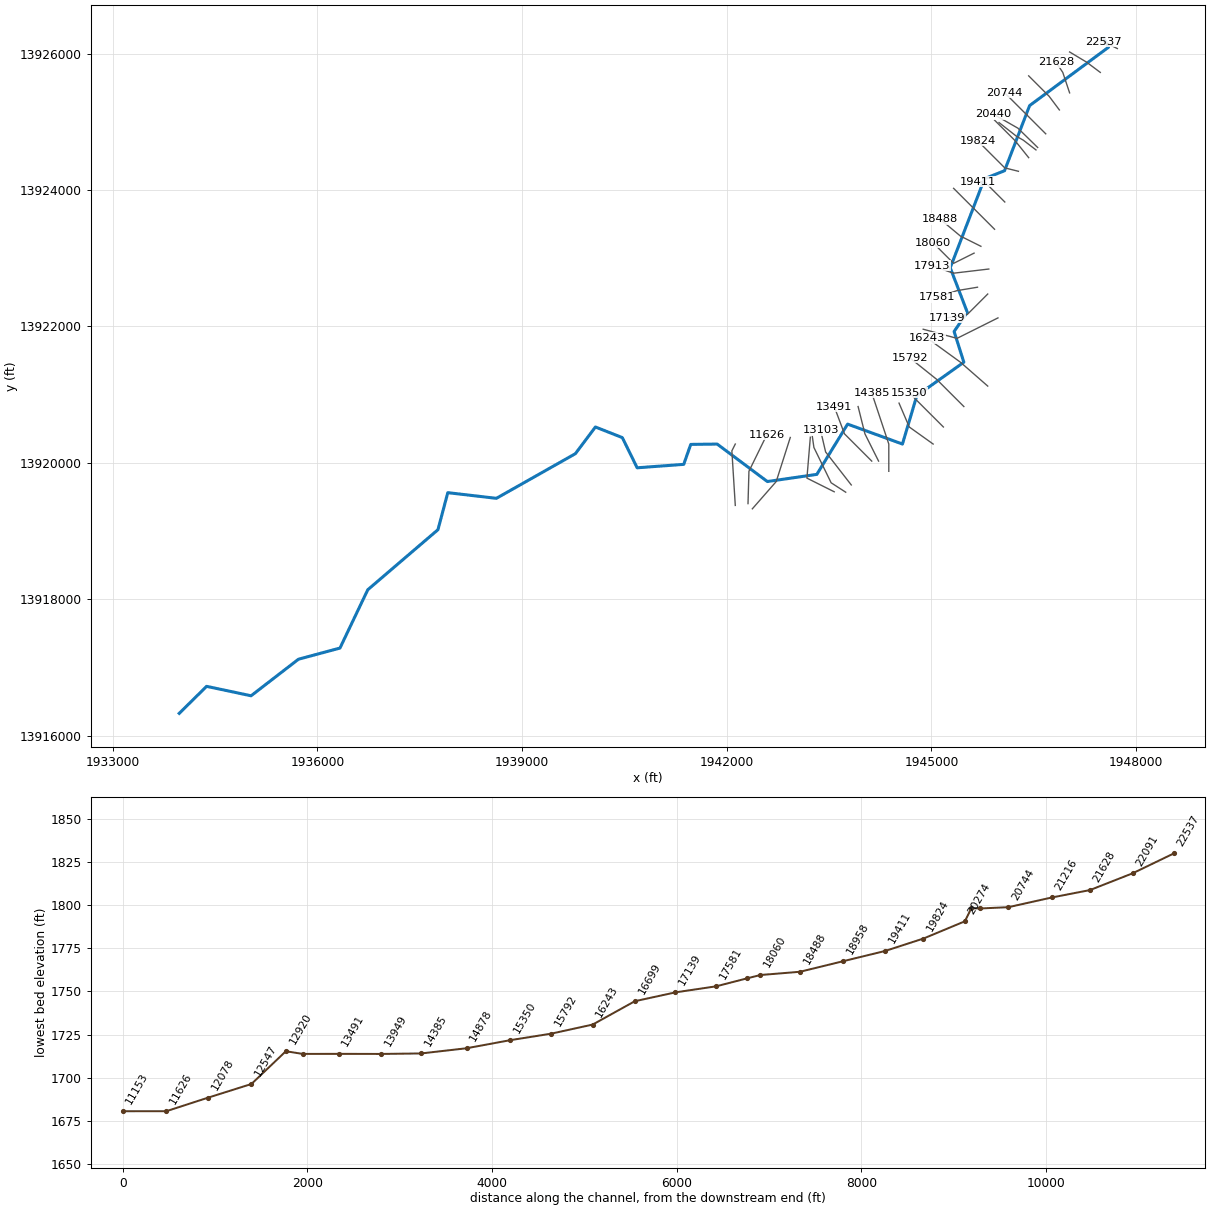
--- Second Creek.prj (project) ---

Proj Title=Second Creek Base Level Engineering
Current Plan=p01
Default Exp/Contr=0.3,0.1
English Units
Geom File=g01
Flow File=f01
Plan File=p01
Y Axis Title=Elevation
X Axis Title(PF)=Main Channel Distance
X Axis Title(XS)=Station
BEGIN DESCRIPTION:
Second Creek
END DESCRIPTION:
DSS Export Rating Curves= 0
DSS Export Rating Curve Sorted= 0
DSS Export Volume Flow Curves= 0
DXF OffsetX= 0
DXF OffsetY= 0
DXF ScaleX= 1
DXF ScaleY= 10

--- Second Creek.p01 (plan) ---

Plan Title=Multiple Run
Short Identifier=Multiple
Geom File=g01
Flow File=f01
Subcritical Flow
K Sum by GR= 0
Std Step Tol= 0.01
Critical Tol= 0.01
Num of Std Step Trials= 20
Max Error Tol= 0.3
Flow Tol Ratio= 0.001
Split Flow NTrial= 30
Split Flow Tol= 0.02
Split Flow Ratio= 0.02
Log Output Level= 0
Friction Slope Method= 1
Unsteady Friction Slope Method= 2
Unsteady Bridges Friction Slope Method= 1
Parabolic Critical Depth
Global Vel Dist=  1 , 1 , 1
Global Log Level= 0
CheckData=True
Encroach Param= -1, 0, 0, 0
BEGIN DESCRIPTION:
Multiple Run
END DESCRIPTION:

--- Second Creek.f01 (steady flow) ---

Flow Title=Multiple
Number of Profiles=7
Profile Names=10-year,25-year,50-year,1pct_min,100-year,1pct_plu,500-year
River Rch & RM= Second Creek,Reach-1,22537
    1500    2597    3657    2489    4967    9910    9043
River Rch & RM= Second Creek,Reach-1,16243
    2862    5115    7357    5102   10179   20310   19252
River Rch & RM= Second Creek,Reach-1,10606
    3078    5513    7942    5513   11001   21949   20855
River Rch & RM= Second Creek,Reach-1,8397
    4224    7687   11190    7838   15639   31204   30209
River Rch & RM= Second Creek,Reach-1,2430
    4452    8114   11820    8284   16528   32978   31962
Boundary for River Rch & Prof#=Second Creek,Reach-1,1
Up Type=0
Dn Type=3
Dn Slope=0.005
Boundary for River Rch & Prof#=Second Creek,Reach-1,2
Up Type=0
Dn Type=3
Dn Slope=0.005
Boundary for River Rch & Prof#=Second Creek,Reach-1,3
Up Type=0
Dn Type=3
Dn Slope=0.005
Boundary for River Rch & Prof#=Second Creek,Reach-1,4
Up Type=0
Dn Type=3
Dn Slope=0.005
Boundary for River Rch & Prof#=Second Creek,Reach-1,5
Up Type=0
Dn Type=3
Dn Slope=0.005
Boundary for River Rch & Prof#=Second Creek,Reach-1,6
Up Type=0
Dn Type=3
Dn Slope=0.005
Boundary for River Rch & Prof#=Second Creek,Reach-1,7
Up Type=0
Dn Type=3
Dn Slope=0.005

--- Second Creek.g01 (geometry) ---

Geom Title=Existing Conditions
Program Version=4.10

River Reach=Second Creek    ,Reach-1
Reach XY= 30
        1947525.       13926225.      1947595.69     13926094.63
      1946438.62     13925238.22       1946071.5     13924283.46
      1945778.06     13924166.72       1945275.5     13922859.76
      1945524.76     13922209.78      1945332.28     13921925.09
        1945475.       13921475.      1944785.78     13920984.68
        1944575.       13920275.       1943771.3     13920567.33
      1943319.96     13919830.09      1942595.03     13919725.07
      1941859.78     13920274.48      1941472.24     13920269.69
      1941369.35     13919976.97      1940686.83     13919926.62
      1940469.41     13920369.39        1940075.       13920525.
      1939781.06     13920133.14      1938623.44     13919478.76
      1937911.34     13919561.83      1937767.19     13919018.81
      1936738.62     13918138.22      1936331.19     13917282.81
       1935722.7     13917119.17      1935028.32     13916583.04
      1934376.46     13916721.47        1933975.       13916325.

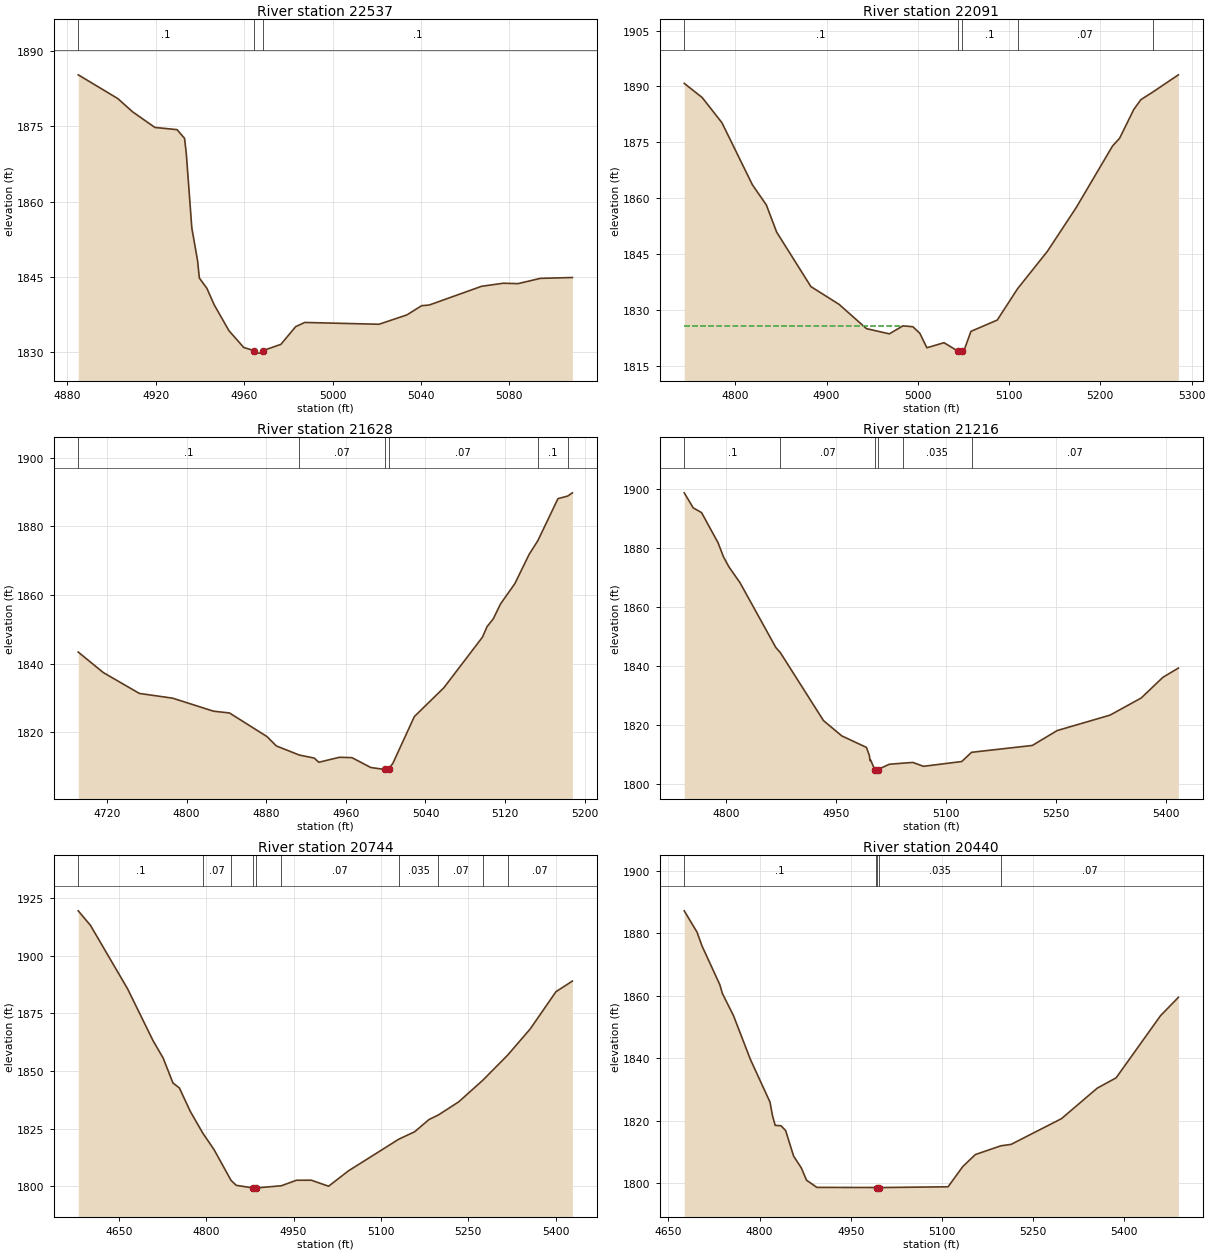
Type RM Length L Ch R = 1 ,22537   ,446,446,446
BEGIN DESCRIPTION:
Second Creek 47.0
END DESCRIPTION:
XS GIS Cut Line= 3
      1947724.98     13926075.01        1947625.       13926125.
      1947524.98     13926175.01
#Sta/Elev= 30
  4884.9 1885.28  4902.8 1880.55  4909.5 1877.91  4919.6  1874.8  4929.6 1874.36
    4933 1872.63  4933.8 1869.57  4936.3 1854.76  4938.9 1848.26  4939.7 1844.81
  4943.1 1842.77  4946.4 1839.49  4953.1 1834.32  4959.8 1830.97  4964.5 1830.35
  4964.8 1829.85  4968.3 1829.85  4968.5 1830.35  4976.6  1831.6  4983.3 1835.13
  4987.4 1835.96    5021  1835.6  5033.6 1837.46  5040.3  1839.3  5043.7 1839.43
  5067.4 1843.16  5077.2 1843.77  5083.9 1843.69    5094 1844.74  5108.5 1844.91
#Mann= 3 ,-1 , 0
  4884.9      .1       0  4964.5     .05       0  4968.5      .1       0
Bank Sta=4964.5,4968.5
XS Rating Curve= 0 ,0
Exp/Cntr=0.3,0.1

Type RM Length L Ch R = 1 ,22091   ,463,463,463
BEGIN DESCRIPTION:
Second Creek 46.0
END DESCRIPTION:
XS GIS Cut Line= 3
      1947474.97     13925725.02        1947275.       13925875.
      1947025.01     13926024.99
#Sta/Elev= 30
    4744 1890.83  4763.7 1887.01  4785.3 1880.26  4818.7 1863.58    4834 1858.16
  4845.3 1850.85  4882.8 1836.23  4913.7 1831.45  4943.7 1824.93  4968.7 1823.53
  4983.7 1825.68  4994.6 1825.44  5002.2 1823.67  5009.9 1819.79  5028.7 1821.15
  5044.2 1818.85  5044.4 1818.35  5048.2 1818.85  5051.2 1819.48  5058.2  1824.2
    5087 1827.23  5109.3 1835.66  5142.1 1845.75  5173.6 1857.48  5213.3 1873.98
  5221.1 1876.08  5236.6  1883.8  5244.4 1886.45  5257.4 1888.48  5285.5 1893.12
#Mann= 5 ,-1 , 0
    4744      .1       0  5044.2     .05       0  5048.2      .1       0
  5109.3     .07       0  5257.4      .1       0
#XS Ineff= 2 , 0
         4983.91 1825.71
Permanent Ineff=
       F       F
Bank Sta=5044.2,5048.2
XS Rating Curve= 0 ,0
Exp/Cntr=0.3,0.1

Type RM Length L Ch R = 1 ,21628   ,412,412,412
BEGIN DESCRIPTION:
Second Creek 45.0
END DESCRIPTION:
XS GIS Cut Line= 3
      1947025.01     13925424.97        1946925.       13925725.
      1946825.02     13925874.97
#Sta/Elev= 30
  4691.1 1843.35  4716.3 1837.37  4752.5 1831.29  4785.9 1829.91    4827 1826.11
  4843.1 1825.59  4880.7 1818.71  4890.2 1815.97  4913.2 1813.32  4928.2 1812.44
  4932.8 1811.21  4953.5 1812.67  4966.1 1812.56  4985.1 1809.68  4998.9 1809.13
  4999.2 1808.63  5002.9 1809.13  5007.4 1811.01  5028.8 1824.54  5058.5 1832.96
  5097.3 1847.73  5101.8 1850.73  5108.2 1853.09  5115.4 1857.39  5129.8 1863.32
  5144.2 1871.87  5152.9 1875.84  5173.1 1888.09    5183 1888.86  5187.6 1889.79
#Mann= 6 ,-1 , 0
  4691.1      .1       0  4913.2     .07       0  4998.9     .05       0
  5002.9     .07       0  5152.9      .1       0    5183     .07       0
Bank Sta=4998.9,5002.9
XS Rating Curve= 0 ,0
Exp/Cntr=0.3,0.1

Type RM Length L Ch R = 1 ,21216   ,472,472,472
BEGIN DESCRIPTION:
Second Creek 44.0
END DESCRIPTION:
XS GIS Cut Line= 3
      1946874.99     13925175.02        1946725.       13925375.
      1946425.03     13925674.97
#Sta/Elev= 30
  4742.5 1898.55  4754.8 1893.45  4766.1 1891.87  4788.6 1881.68  4796.1 1876.86
  4803.6 1873.44  4818.6 1868.13  4867.5 1846.19  4873.7 1844.43  4932.5 1821.45
  4957.5 1816.27  4991.1 1812.38  4995.1 1809.64    4996 1807.92  4996.8 1808.13
  5002.4 1804.85  5002.7 1804.35  5006.4 1804.85  5022.2 1806.67  5041.4 1807.06
  5054.5 1807.29  5068.9 1805.98  5121.1  1807.6  5134.5 1810.72  5217.4 1813.04
  5251.3 1818.08  5323.5 1823.31  5365.9 1829.09  5395.6 1836.11  5416.7 1839.23
#Mann= 6 ,-1 , 0
  4742.5      .1       0  4873.7     .07       0  5002.4     .05       0
  5006.4     .07       0  5041.4    .035       0  5134.5     .07       0
Bank Sta=5002.4,5006.4
XS Rating Curve= 0 ,0
Exp/Cntr=0.3,0.1

Type RM Length L Ch R = 1 ,20744   ,304,304,304
BEGIN DESCRIPTION:
Second Creek 43.0
END DESCRIPTION:
XS GIS Cut Line= 3
      1946674.97     13924825.03        1946375.       13925125.
      1946074.99     13925425.01
#Sta/Elev= 30
  4580.3 1919.54  4601.3 1913.22  4664.9 1885.74    4709 1863.05    4726 1855.68
  4742.9 1844.83    4754 1842.63  4772.6 1832.53  4794.2 1823.03  4813.4 1815.93
  4842.7 1802.52  4851.6 1800.38    4881 1799.23  4881.2 1798.73    4885 1799.23
    4929 1800.19  4955.1 1802.59  4980.5  1802.6  5010.2 1799.99  5044.2 1806.65
  5130.7 1820.41  5157.9 1823.62  5182.5 1828.92  5198.7 1830.92  5233.4 1836.58
  5274.7 1845.93  5317.8 1856.94  5356.5 1868.31  5400.6 1884.43  5428.8 1889.05
#Mann= 10 ,-1 , 0
  4580.3      .1       0  4794.2     .07       0  4842.7    .035       0
    4881     .05       0    4885    .035       0    4929     .07       0
  5130.7    .035       0  5198.7     .07       0  5274.7    .035       0
  5317.8     .07       0
Bank Sta=4881,4885
XS Rating Curve= 0 ,0
Exp/Cntr=0.3,0.1

Type RM Length L Ch R = 1 ,20440   ,97,97,97
BEGIN DESCRIPTION:
Mapping XS b5a05388
END DESCRIPTION:
XS GIS Cut Line= 3
      1946556.86     13924624.16      1946267.67     13924907.12
      1945912.99       13925110.
#Sta/Elev= 30
    4676 1887.25    4697 1880.44  4705.2 1876.01  4734.6 1863.55  4738.8 1860.73
  4757.1 1853.61    4785 1839.54  4817.1 1825.92  4821.4 1821.44  4825.7 1818.44
  4835.3 1818.32  4842.9 1816.77    4856 1808.57  4868.6 1804.83  4877.3 1800.85
  4894.3 1798.55  4990.9 1798.51  4992.8 1798.49  4993.1 1797.99  4996.8 1798.49
  5110.2 1798.74  5134.4 1805.23  5155.1 1809.08  5197.1 1811.89  5213.9 1812.34
  5296.8 1820.59  5355.7 1830.38  5386.7 1833.68    5460 1853.66  5489.2  1859.5
#Mann= 5 ,-1 , 0
    4676      .1       0  4990.9    .035       0  4992.8    .035       0
  4996.8    .035       0  5197.1     .07       0
Bank Sta=4992.8,4996.8
XS Rating Curve= 0 ,0
Exp/Cntr=0.3,0.1

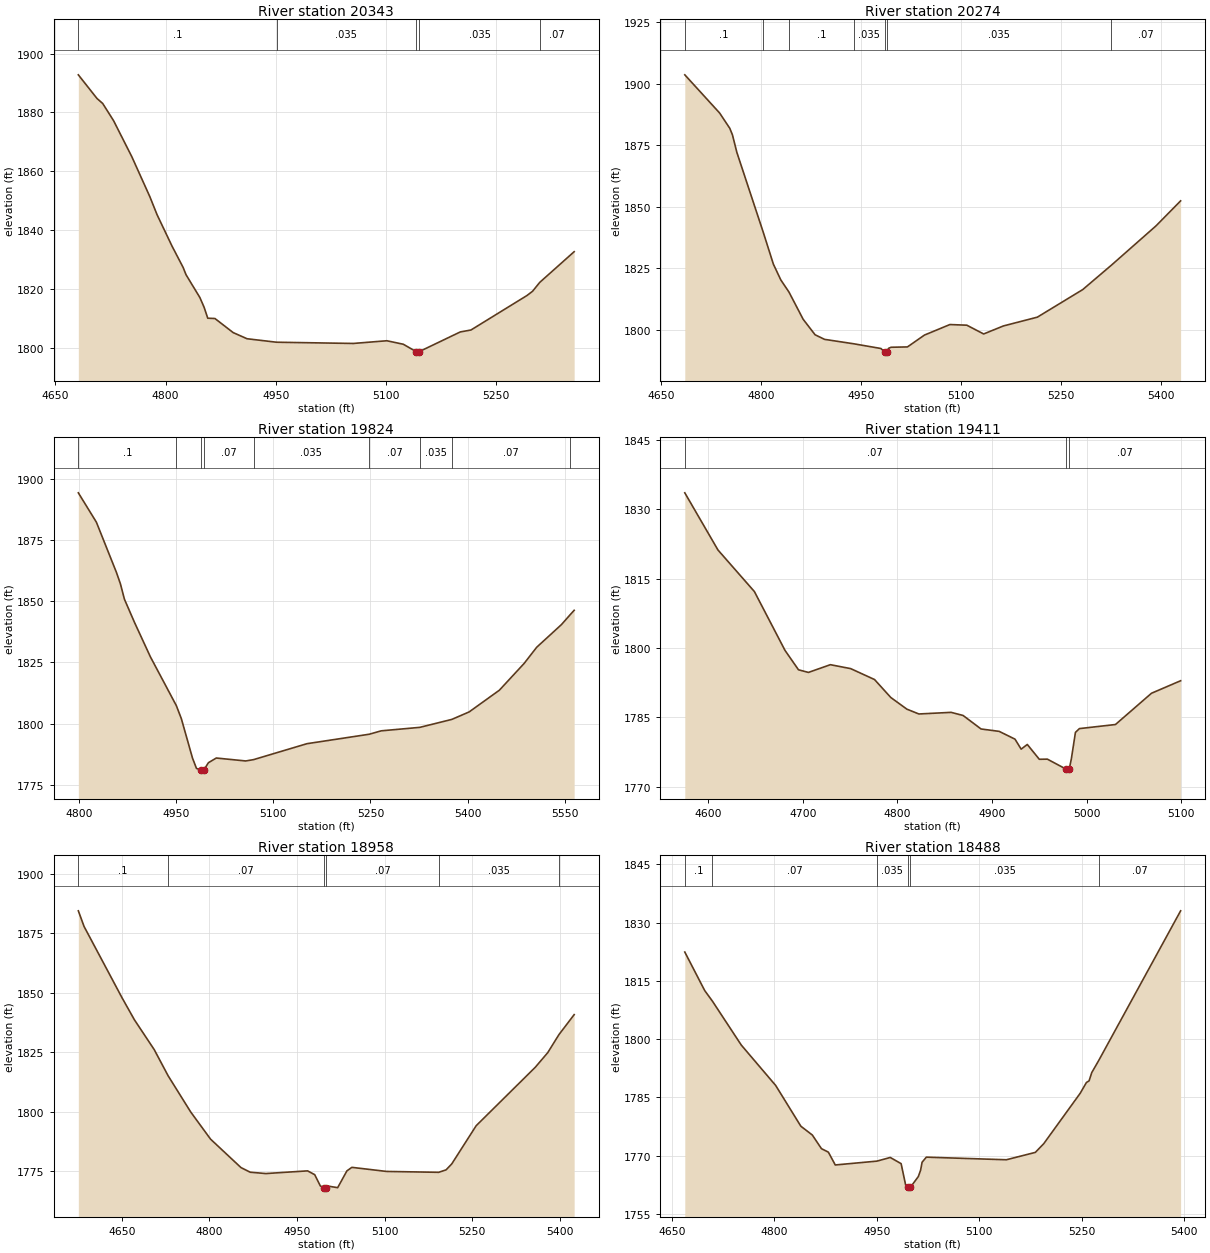
Type RM Length L Ch R = 1 ,20343   ,69,69,69
BEGIN DESCRIPTION:
Second Creek 42.1
END DESCRIPTION:
XS GIS Cut Line= 4
      1946532.11     13924588.53      1946344.62     13924732.62
      1946249.14     13924786.44      1945990.43     13924989.58
#Sta/Elev= 30
  4681.3 1892.78  4706.7 1884.74  4714.5 1883.03  4729.3 1877.18  4754.1 1864.94
  4778.6 1851.37  4788.5  1845.2  4808.9  1834.5    4824 1827.25  4827.9  1824.8
  4846.7 1817.06  4852.5 1813.74  4857.5    1810  4867.3 1809.89  4892.1  1805.1
    4911 1803.01  4951.1 1801.83  5055.6 1801.41  5101.3 1802.33  5123.6 1801.15
  5141.3 1798.62  5141.5 1798.12    5145 1798.12  5145.3 1798.62  5201.3 1805.33
  5215.8 1805.98  5292.1 1817.72  5299.7 1819.17  5309.4 1822.17  5356.3 1832.62
#Mann= 5 ,-1 , 0
  4681.3      .1       0  4951.1    .035       0  5141.3    .035       0
  5145.3    .035       0  5309.4     .07       0
Bank Sta=5141.3,5145.3
XS Rating Curve= 0 ,0
Exp/Cntr=0.3,0.1

Type RM Length L Ch R = 1 ,20274   ,450,450,450
BEGIN DESCRIPTION:
Second Creek 42.0
END DESCRIPTION:
XS GIS Cut Line= 3
      1946424.99     13924475.01        1946225.       13924725.
        1945925.       13925025.
#Sta/Elev= 30
    4685 1903.55  4737.3 1888.05  4752.5 1881.86  4756.5 1879.21  4763.2 1872.04
  4802.9 1839.55    4818  1826.7  4829.1 1820.32  4841.4 1815.37  4862.7 1804.32
  4880.6 1798.03  4894.8 1796.17  4938.7 1794.37  4979.4 1792.46    4985 1791.08
  4985.3 1790.58    4989 1791.08  4990.9 1792.53  4994.7 1792.96  5019.3  1793.1
  5044.8 1797.91    5083 1802.18  5108.4 1801.92  5133.7 1798.36  5163.3 1801.61
  5214.3 1805.18  5282.4 1816.37  5325.6 1826.31  5392.5 1842.25  5429.4 1852.39
#Mann= 7 ,-1 , 0
    4685      .1       0  4802.9    .035       0  4841.4      .1       0
  4938.7    .035       0    4985    .035       0    4989    .035       0
  5325.6     .07       0
Bank Sta=4985,4989
XS Rating Curve= 0 ,0
Exp/Cntr=0.3,0.1

Type RM Length L Ch R = 1 ,19824   ,413,413,413
BEGIN DESCRIPTION:
Second Creek 41.0
END DESCRIPTION:
XS GIS Cut Line= 3
        1946275.       13924275.        1946075.       13924325.
      1945679.04      13924720.5
#Sta/Elev= 30
  4798.8  1894.2  4826.7 1882.21  4857.6 1861.74  4863.8 1857.05    4870 1850.77
  4885.4 1841.39  4910.2 1827.19  4950.2  1807.3  4957.9    1802  4975.1 1785.92
  4981.3 1781.66  4988.6 1781.07  4988.8 1780.57  4992.6 1781.07  4999.8 1784.02
  5011.9 1785.92  5057.3 1784.72  5069.4 1785.26  5151.9 1791.77    5248 1795.63
  5266.6 1797.02  5326.2 1798.44  5375.6 1801.68  5402.4 1804.74  5449.1 1813.61
  5487.3 1824.53  5506.8 1831.16  5544.9 1840.38  5558.7 1844.51  5564.6 1846.23
#Mann= 9 ,-1 , 0
  4798.8      .1       0  4950.2     .07       0  4988.6     .05       0
  4992.6     .07       0  5069.4    .035       0    5248     .07       0
  5326.2    .035       0  5375.6     .07       0  5558.7    .035       0
Bank Sta=4988.6,4992.6
XS Rating Curve= 0 ,0
Exp/Cntr=0.3,0.1

Type RM Length L Ch R = 1 ,19411   ,453,453,453
BEGIN DESCRIPTION:
Second Creek 40.0
END DESCRIPTION:
XS GIS Cut Line= 3
      1946074.98     13923825.02        1945775.       13924125.
      1945675.03       13924125.
#Sta/Elev= 30
  4575.2 1833.55  4610.3 1821.19  4648.8 1812.21  4681.2 1799.48  4695.4 1795.31
  4705.9 1794.74  4729.1 1796.41  4750.6 1795.56  4775.8  1793.2    4793 1789.32
    4810  1786.8  4822.7 1785.76  4856.7 1786.11  4869.4 1785.44  4888.4 1782.52
  4907.6    1782  4924.3 1780.32  4930.8 1778.16  4937.3 1779.17    4950 1775.97
  4958.5    1776  4977.7 1773.91  4977.9 1773.41  4981.7 1773.91  4983.9 1776.08
  4988.2 1781.78  4992.4  1782.6  5030.5 1783.48  5068.6 1790.24  5099.4 1792.94
#Mann= 3 ,-1 , 0
  4575.2     .07       0  4977.7     .05       0  4981.7     .07       0
Bank Sta=4977.7,4981.7
XS Rating Curve= 0 ,0
Exp/Cntr=0.3,0.1

Type RM Length L Ch R = 1 ,18958   ,470,470,470
BEGIN DESCRIPTION:
Second Creek 39.0
END DESCRIPTION:
XS GIS Cut Line= 3
      1945924.97     13923425.03        1945625.       13923725.
      1945324.99     13924025.01
#Sta/Elev= 30
  4575.8 1884.41  4585.7  1877.8  4650.5 1847.93  4671.7 1838.67  4705.7  1826.1
  4729.4 1815.15  4768.1 1799.92  4802.1  1788.5  4854.2 1776.55    4870 1774.61
  4896.6 1774.05  4968.1 1775.18  4980.3 1773.58  4989.9 1768.87  4996.4 1768.01
  4996.7 1767.51  5000.4 1768.01  5002.7  1768.8  5019.6 1768.12  5035.4 1775.17
  5043.9 1776.66  5103.3 1774.94  5192.4 1774.57  5205.1  1775.6  5214.8 1778.09
  5256.6 1794.14  5357.9 1818.73  5379.1 1824.84  5398.3 1832.42  5424.3  1840.8
#Mann= 6 ,-1 , 0
  4575.8      .1       0  4729.4     .07       0  4996.4     .05       0
  5000.4     .07       0  5192.4    .035       0  5398.3     .07       0
Bank Sta=4996.4,5000.4
XS Rating Curve= 0 ,0
Exp/Cntr=0.3,0.1

Type RM Length L Ch R = 1 ,18488   ,428,428,428
BEGIN DESCRIPTION:
Second Creek 38.0
END DESCRIPTION:
XS GIS Cut Line= 3
      1945724.96     13923175.02        1945425.       13923325.
      1945124.99     13923575.01
#Sta/Elev= 30
  4668.8  1822.4  4697.9  1812.5  4709.3 1809.74  4751.5 1798.45  4801.9 1788.04
  4838.7 1777.56  4855.5 1775.29  4868.9 1771.77    4879 1770.88  4889.1 1767.58
  4950.1 1768.57  4969.6 1769.51  4985.5 1767.92  4992.2 1762.36  4995.2 1761.86
  4995.4 1761.36  4999.2 1761.86  5010.7  1764.6    5014 1766.21  5016.2 1768.28
  5022.4 1769.59  5139.6 1768.92    5182 1770.82  5194.3 1773.06  5247.6 1786.02
  5256.8 1788.81  5260.7 1789.24  5264.6 1791.36  5274.9 1794.51  5394.7 1833.01
#Mann= 6 ,-1 , 0
  4668.8      .1       0  4709.3     .07       0  4950.1    .035       0
  4995.2    .035       0  4999.2    .035       0  5274.9     .07       0
Bank Sta=4995.2,4999.2
XS Rating Curve= 0 ,0
Exp/Cntr=0.3,0.1

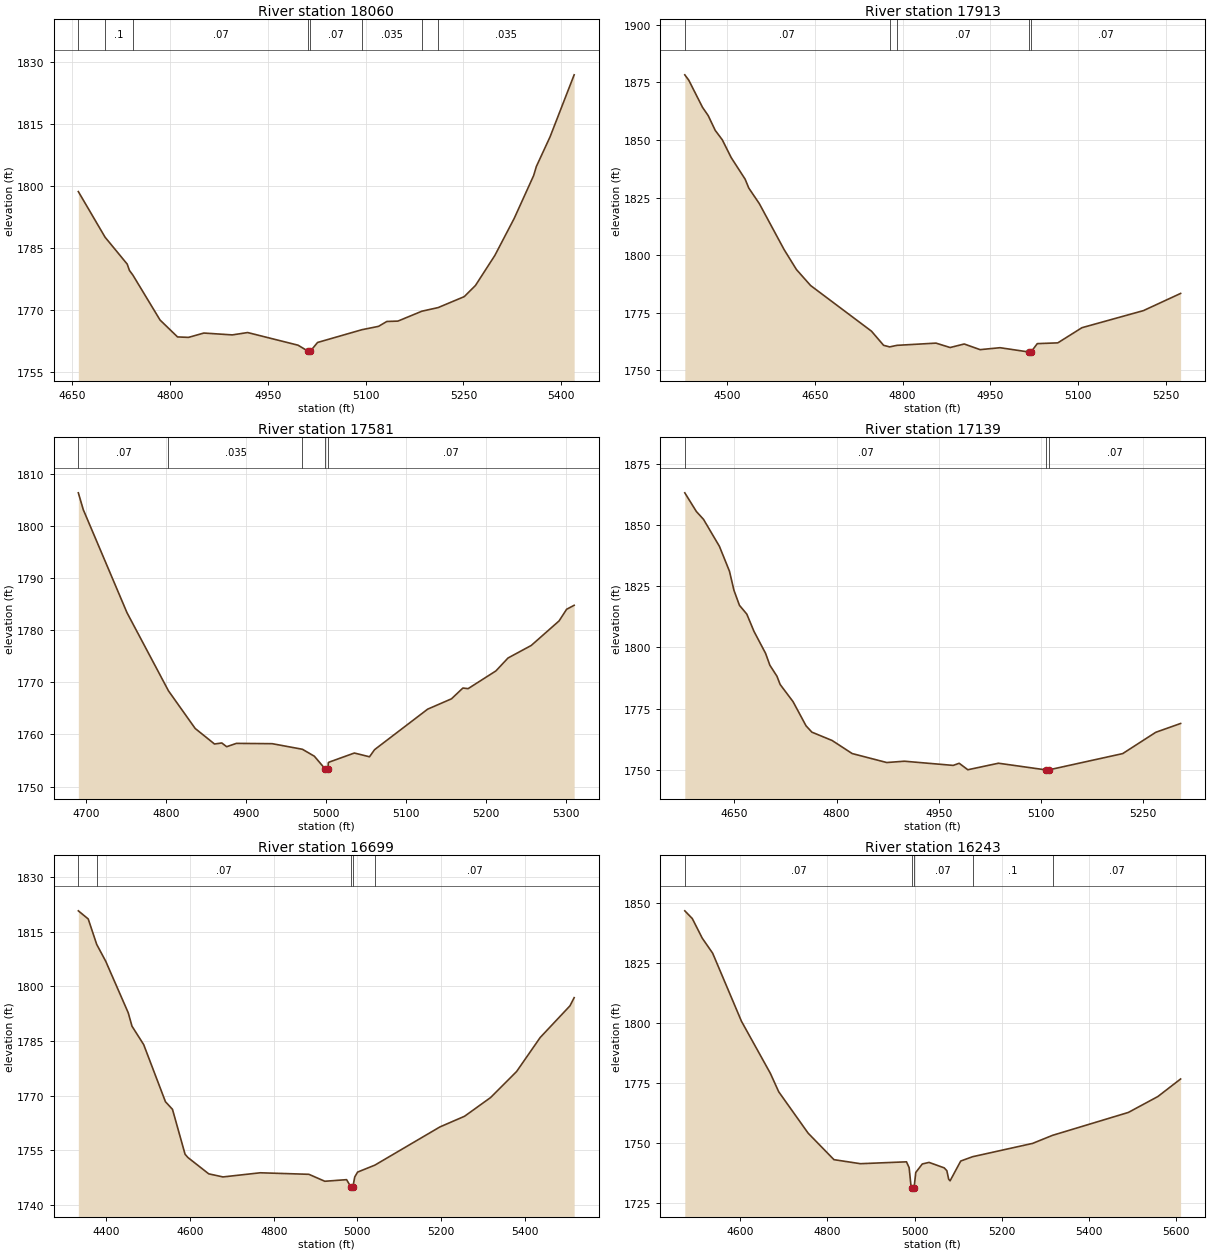
Type RM Length L Ch R = 1 ,18060   ,147,147,147
BEGIN DESCRIPTION:
Second Creek 37.0
END DESCRIPTION:
XS GIS Cut Line= 3
      1945624.96     13923074.98        1945325.       13922925.
      1945025.02     13923224.98
#Sta/Elev= 30
    4660 1798.58    4701 1787.54  4734.9 1781.03  4738.3  1779.5  4743.6 1778.37
  4785.2  1767.5    4812 1763.41  4828.8  1763.3  4852.3 1764.35  4895.9  1763.9
  4919.4 1764.47  4996.6 1761.41  5011.6 1759.99  5011.8 1759.49  5015.6 1759.99
  5026.5 1762.07  5094.5 1765.16  5119.9 1765.97  5132.6 1767.15  5149.6 1767.24
  5186.4 1769.64  5211.2 1770.51  5251.2 1773.16  5268.4 1775.86  5298.1 1783.13
  5327.8 1792.11  5357.5 1802.45  5361.7 1804.66  5382.7 1811.84  5419.6 1826.84
#Mann= 8 ,-1 , 0
    4660     .07       0    4701      .1       0  4743.6     .07       0
  5011.6     .05       0  5015.6     .07       0  5094.5    .035       0
  5186.4     .07       0  5211.2    .035       0
Bank Sta=5011.6,5015.6
XS Rating Curve= 0 ,0
Exp/Cntr=0.3,0.1

Type RM Length L Ch R = 1 ,17913   ,332,332,332
BEGIN DESCRIPTION:
Mapping XS 94cf64ff
END DESCRIPTION:
XS GIS Cut Line= 3
      1945840.69     13922841.75      1945320.84     13922780.29
      1945015.13     13922889.78
#Sta/Elev= 30
  4427.3 1878.22  4434.1 1875.89  4457.6 1864.13  4467.3 1860.56  4479.4 1854.12
  4491.5 1850.02  4506.6 1842.36  4530.5 1832.98  4536.8  1829.1  4554.8 1822.36
  4597.2 1802.43  4618.3 1793.78  4642.5 1786.85  4746.6 1767.06  4767.4 1760.92
  4777.8 1760.23    4790  1760.9    4857 1761.87  4881.2 1759.96  4905.3 1761.49
  4932.5 1759.04  4966.6 1759.88  5015.6 1758.03  5015.8 1757.53  5019.6 1758.03
  5030.3 1761.65  5065.4 1761.98  5106.7 1768.56  5211.9 1775.97  5275.5 1783.42
#Mann= 5 ,-1 , 0
  4427.3     .07       0  4777.8    .035       0    4790     .07       0
  5015.6     .05       0  5019.6     .07       0
Bank Sta=5015.6,5019.6
XS Rating Curve= 0 ,0
Exp/Cntr=0.3,0.1

Type RM Length L Ch R = 1 ,17581   ,442,442,442
BEGIN DESCRIPTION:
Second Creek 36.0
END DESCRIPTION:
XS GIS Cut Line= 3
      1945675.04     13922575.01        1945375.       13922525.
      1945075.01       13922425.
#Sta/Elev= 30
    4690  1806.3  4696.2 1803.07  4750.9 1783.32  4802.8 1768.34  4836.2 1761.13
  4860.4 1758.15  4869.5 1758.35  4875.6 1757.63  4887.8 1758.27  4932.6 1758.21
  4970.4 1757.14  4985.3 1755.81  4998.4 1753.45  4998.7 1752.95  5002.4 1753.45
  5002.8 1754.58  5003.7 1754.67  5035.4 1756.42  5054.3  1755.7  5060.7 1757.07
  5127.1 1764.83  5156.9 1766.81  5171.2 1768.88  5177.7 1768.76  5212.5 1772.16
  5227.6 1774.63  5256.7 1777.04  5291.5 1781.74    5301 1783.98  5310.4 1784.74
#Mann= 5 ,-1 , 0
    4690     .07       0  4802.8    .035       0  4970.4     .07       0
  4998.4     .05       0  5002.4     .07       0
Bank Sta=4998.4,5002.4
XS Rating Curve= 0 ,0
Exp/Cntr=0.3,0.1

Type RM Length L Ch R = 1 ,17139   ,440,440,440
BEGIN DESCRIPTION:
Second Creek 35.0
END DESCRIPTION:
XS GIS Cut Line= 3
      1945824.97     13922474.97        1945525.       13922175.
      1945224.96     13922124.99
#Sta/Elev= 30
    4577 1863.14    4594 1855.51  4604.5  1852.3  4627.8 1841.32  4642.6 1831.14
  4649.2 1823.33  4657.3 1817.17  4668.1 1813.59  4678.7 1806.51  4695.7 1797.55
    4702 1792.69  4712.4 1788.21  4717.1 1784.83    4736 1777.84  4755.1 1767.96
  4763.7 1765.36  4793.4 1761.96  4822.9 1756.62  4873.7 1752.95  4899.5 1753.49
  4971.3 1751.78  4980.1 1752.65  4992.8    1750  5037.8 1752.67  5107.6 1749.94
  5107.8 1749.44  5111.6 1749.94  5220.3  1756.6  5268.9 1765.31  5305.4 1768.91
#Mann= 3 ,-1 , 0
    4577     .07       0  5107.6     .05       0  5111.6     .07       0
Bank Sta=5107.6,5111.6
XS Rating Curve= 0 ,0
Exp/Cntr=0.3,0.1

Type RM Length L Ch R = 1 ,16699   ,456,456,456
BEGIN DESCRIPTION:
Second Creek 34.0
END DESCRIPTION:
XS GIS Cut Line= 3
      1945975.03     13922125.02        1945375.       13921825.
      1944879.22     13921958.89
#Sta/Elev= 30
  4333.3 1820.78  4356.9 1818.55  4377.2 1811.56  4398.8 1806.91  4452.5 1792.77
  4461.5 1789.08  4489.4 1784.03  4541.4 1768.34  4558.2 1766.24  4588.3  1753.9
    4595 1753.01  4644.8 1748.52  4678.9 1747.67  4767.8 1748.81  4884.1 1748.39
  4922.1 1746.48  4974.1 1746.92  4984.9 1744.82  4985.2 1744.32  4988.9 1744.82
  4993.6 1747.66  5000.4    1749  5041.6 1750.91  5196.9  1761.4  5255.9 1764.34
  5318.1 1769.48  5380.2 1776.63  5436.6 1785.98  5507.7 1794.68  5517.7 1796.92
#Mann= 5 ,-1 , 0
  4333.3      .1       0  4377.2     .07       0  4984.9     .05       0
  4988.9     .07       0  5041.6     .07       0
Bank Sta=4984.9,4988.9
XS Rating Curve= 0 ,0
Exp/Cntr=0.3,0.1

Type RM Length L Ch R = 1 ,16243   ,451,451,451
BEGIN DESCRIPTION:
Second Creek 33.0
END DESCRIPTION:
XS GIS Cut Line= 3
      1945825.02     13921124.99        1945425.       13921475.
      1944935.28     13921830.88
#Sta/Elev= 30
    4473 1846.71  4490.2 1843.49    4513 1835.33  4536.9 1829.06  4602.9 1800.73
  4669.2 1779.03  4688.4 1771.34  4755.8 1754.12    4815 1743.08  4875.7  1741.4
  4981.3 1742.18  4987.4 1739.74  4991.3 1732.79  4993.7 1731.31  4994.1 1730.81
  4998.7 1731.31  5002.6 1737.75  5017.6 1741.29  5033.1 1741.94  5067.8 1739.66
  5073.9 1738.48    5078 1734.98  5081.3 1734.27  5105.7 1742.51  5132.7  1744.3
  5270.4 1749.85  5316.2 1753.21  5490.1 1762.75  5557.7 1769.37  5609.9 1776.69
#Mann= 5 ,-1 , 0
    4473     .07       0  4993.7     .05       0  4998.7     .07       0
  5132.7      .1       0  5316.2     .07       0
Bank Sta=4993.7,4998.7
XS Rating Curve= 0 ,0
Exp/Cntr=0.3,0.1

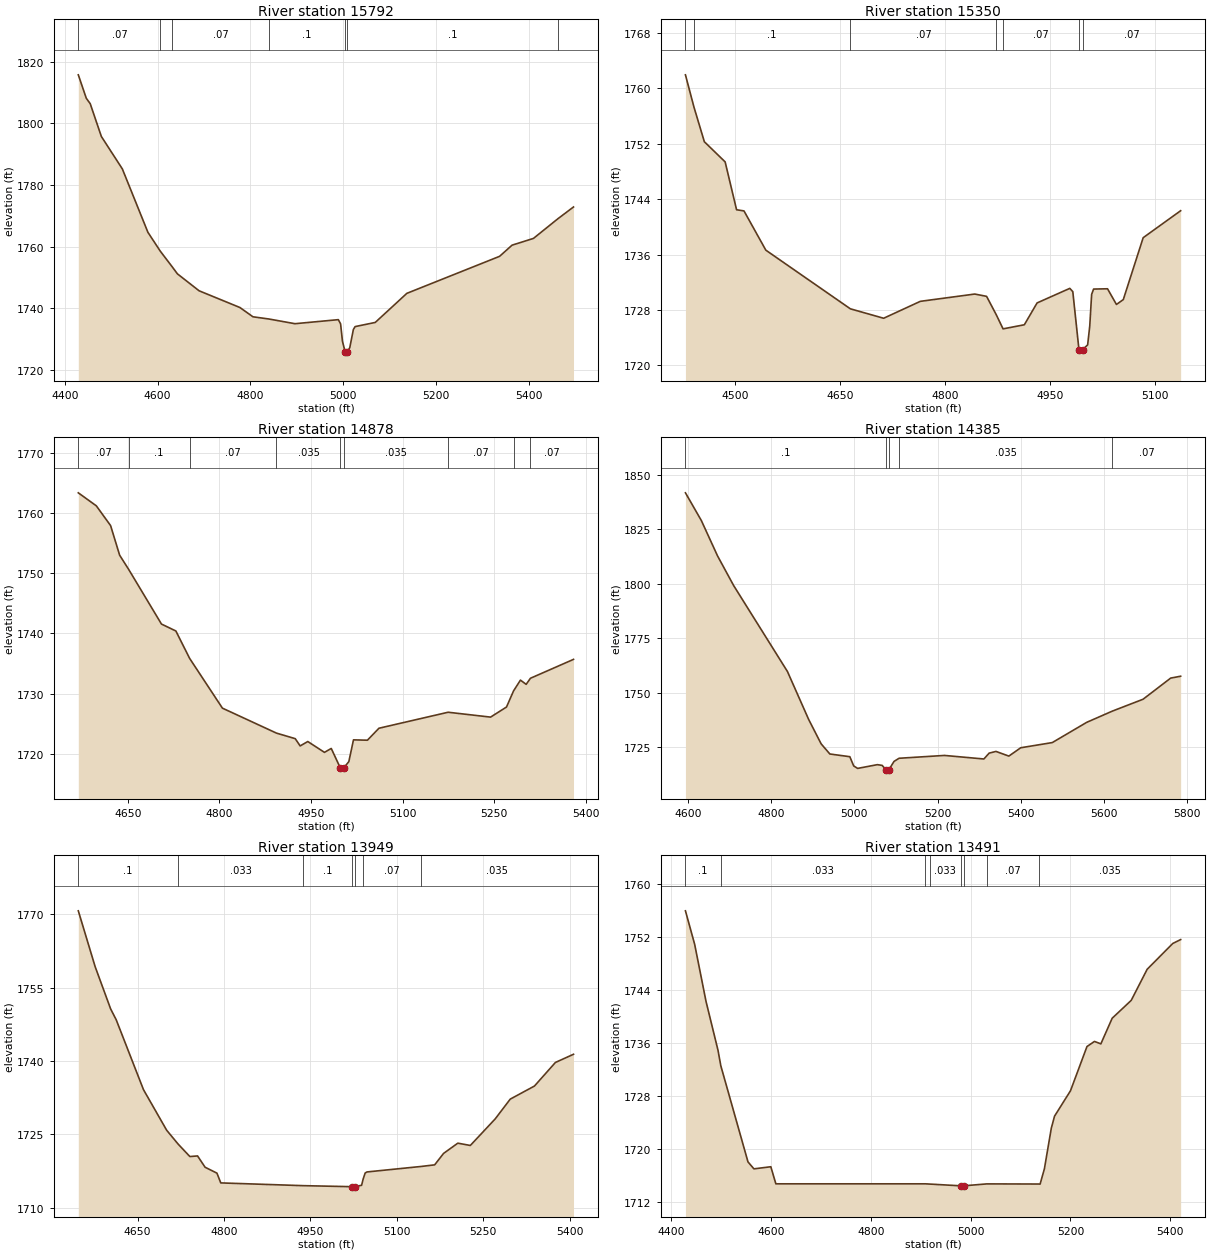
Type RM Length L Ch R = 1 ,15792   ,442,442,442
BEGIN DESCRIPTION:
Second Creek 32.0
END DESCRIPTION:
XS GIS Cut Line= 3
      1945474.99     13920825.01        1945075.       13921225.
      1944683.56     13921538.37
#Sta/Elev= 30
  4429.2 1815.75  4446.4 1808.16  4454.9 1806.39  4478.9 1795.76  4524.1 1785.25
  4579.2  1764.7    4606 1758.56  4630.7 1753.68  4642.8 1751.23  4689.5 1745.74
  4777.4 1740.32  4805.6 1737.31  4840.4 1736.58  4896.1 1735.07  4989.5 1736.38
  4994.4 1735.03  4998.4 1729.39    5004 1726.03  5004.3 1725.53  5009.1 1726.03
  5014.2 1727.31  5021.9 1733.17  5025.7 1734.13  5069.1 1735.48  5137.2 1744.91
    5337 1756.91  5363.9 1760.53    5410 1762.72  5463.2 1769.16  5496.3 1772.91
#Mann= 7 ,-1 , 0
  4429.2     .07       0    4606      .1       0  4630.7     .07       0
  4840.4      .1       0    5004     .05       0  5009.1      .1       0
  5463.2     .07       0
Bank Sta=5004,5009.1
XS Rating Curve= 0 ,0
Exp/Cntr=0.3,0.1

Type RM Length L Ch R = 1 ,15350   ,472,472,472
BEGIN DESCRIPTION:
Second Creek 31.0
END DESCRIPTION:
XS GIS Cut Line= 3
      1945174.99     13920525.01        1944775.       13920925.
        1944675.       13921025.
#Sta/Elev= 30
  4429.5 1761.92  4441.7 1757.25  4456.5 1752.27  4486.2 1749.36  4502.5 1742.46
  4513.1 1742.29  4544.3 1736.63    4665 1728.17  4712.5 1726.81  4764.9 1729.25
  4842.6  1730.3  4859.5 1729.97  4873.4  1727.3    4883 1725.28  4913.4 1725.87
  4931.6 1729.02  4978.3 1731.12  4982.6 1730.65  4991.4 1722.28  4991.8 1721.78
  4996.6 1722.28  5003.8 1722.97  5006.8 1725.68  5009.5 1730.25  5012.3 1731.02
  5032.2 1731.06  5044.9  1728.8  5054.7  1729.5  5083.1 1738.43  5136.6 1742.32
#Mann= 7 ,-1 , 0
  4429.5     .07       0  4441.7      .1       0    4665     .07       0
  4873.4    .035       0    4883     .07       0  4991.4     .05       0
  4996.6     .07       0
Bank Sta=4991.4,4996.6
XS Rating Curve= 0 ,0
Exp/Cntr=0.3,0.1

Type RM Length L Ch R = 1 ,14878   ,493,493,493
BEGIN DESCRIPTION:
Second Creek 30.0
END DESCRIPTION:
XS GIS Cut Line= 3
      1945024.97     13920275.02        1944675.       13920525.
      1944524.99     13920875.03
#Sta/Elev= 30
  4568.9 1763.38  4598.4 1761.22  4621.8 1757.93  4636.6 1753.01  4651.3 1750.66
  4705.1 1741.56  4728.7 1740.41  4751.1 1735.87  4804.9 1727.58  4893.4 1723.43
  4924.1 1722.51  4932.2  1721.3  4944.7 1722.03    4972 1720.23  4983.1 1720.88
  4998.1 1717.61  4998.5 1717.11  5003.3 1717.61  5011.9 1718.69  5019.5 1722.31
  5042.3 1722.25  5061.2 1724.24  5174.5  1726.9    5244 1726.09  5270.1 1727.77
  5281.6 1730.44  5292.9 1732.24  5302.3 1731.54  5309.3 1732.55  5379.8 1735.69
#Mann= 9 ,-1 , 0
  4568.9     .07       0  4651.3      .1       0  4751.1     .07       0
  4893.4    .035       0  4998.1    .035       0  5003.3    .035       0
  5174.5     .07       0  5281.6    .035       0  5309.3     .07       0
Bank Sta=4998.1,5003.3
XS Rating Curve= 0 ,0
Exp/Cntr=0.3,0.1

Type RM Length L Ch R = 1 ,14385   ,436,436,436
BEGIN DESCRIPTION:
Second Creek 29.0
END DESCRIPTION:
XS GIS Cut Line= 3
        1944375.     13919874.95        1944375.       13920275.
      1944125.01     13921024.98
#Sta/Elev= 30
  4593.9 1841.79  4632.1 1829.09  4671.1 1812.84  4710.1 1799.15  4839.1 1759.82
  4890.1 1737.83  4920.1 1726.63  4941.1 1721.96  4989.1 1720.72  4998.4 1716.49
  5007.9 1715.35  5055.3 1717.07  5066.9 1716.73  5076.4  1714.6  5076.9  1714.1
  5082.6  1714.6  5095.4 1718.56  5107.5    1720  5216.6  1721.3  5311.4 1719.67
  5324.1 1722.36  5340.4 1723.14  5371.5    1721    5400 1724.82  5475.9  1727.2
  5558.6 1736.48  5620.5 1741.65  5694.1 1747.08  5760.5 1756.78  5784.5 1757.65
#Mann= 5 ,-1 , 0
  4593.9      .1       0  5076.4     .05       0  5082.6      .1       0
  5107.5    .035       0  5620.5     .07       0
Bank Sta=5076.4,5082.6
XS Rating Curve= 0 ,0
Exp/Cntr=0.3,0.1

Type RM Length L Ch R = 1 ,13949   ,458,458,458
BEGIN DESCRIPTION:
Second Creek 28.0
END DESCRIPTION:
XS GIS Cut Line= 3
        1944225.     13920025.01        1944025.       13920425.
        1943925.     13920824.98
#Sta/Elev= 30
  4547.2 1770.67  4576.5 1759.24  4603.3 1750.64    4613 1748.41  4660.3 1734.14
  4700.6 1725.84  4720.5 1723.01  4740.8 1720.47  4754.2 1720.59  4767.3 1718.28
  4787.8 1717.08  4794.5 1715.08    4937 1714.52  5021.7 1714.31  5022.2 1713.81
  5027.9 1714.31  5038.9  1714.6  5041.6 1715.87  5045.1  1717.1  5048.2 1717.32
  5142.2 1718.44  5165.7 1718.77  5181.2 1721.11  5205.9  1723.2  5227.6 1722.73
  5270.8 1728.16  5296.9  1732.2  5338.9 1734.87  5375.3 1739.69  5406.7 1741.36
#Mann= 7 ,-1 , 0
  4547.2      .1       0  4720.5    .033       0    4937      .1       0
  5021.7     .05       0  5027.9      .1       0  5041.6     .07       0
  5142.2    .035       0
Bank Sta=5021.7,5027.9
XS Rating Curve= 0 ,0
Exp/Cntr=0.3,0.1

Type RM Length L Ch R = 1 ,13491   ,388,388,388
BEGIN DESCRIPTION:
Second Creek 27.0
END DESCRIPTION:
XS GIS Cut Line= 3
        1944125.       13920025.        1943725.       13920425.
        1943575.     13920825.01
#Sta/Elev= 30
  4428.1 1755.89  4446.6 1750.83  4469.4  1742.2  4493.3 1734.86    4499  1732.5
  4553.5 1717.98  4565.4 1716.93  4599.3 1717.25  4609.4 1714.67  4909.3 1714.67
  4918.7 1714.63  4979.6 1714.37  4980.1 1713.87  4985.4 1713.87  4985.9 1714.37
  5032.5 1714.66  5136.3 1714.64  5139.2 1714.63  5147.8 1716.94  5161.7 1723.08
  5168.1 1724.88  5200.1 1728.72  5233.2  1735.4  5248.2 1736.17    5261  1735.8
  5283.7 1739.67  5321.9 1742.37  5353.9 1747.07  5405.2 1750.96    5421 1751.55
#Mann= 8 ,-1 , 0
  4428.1      .1       0    4499    .033       0  4909.3      .1       0
  4918.7    .033       0  4979.6    .033       0  4985.9    .033       0
  5032.5     .07       0  5136.3    .035       0
Bank Sta=4979.6,4985.9
XS Rating Curve= 0 ,0
Exp/Cntr=0.3,0.1

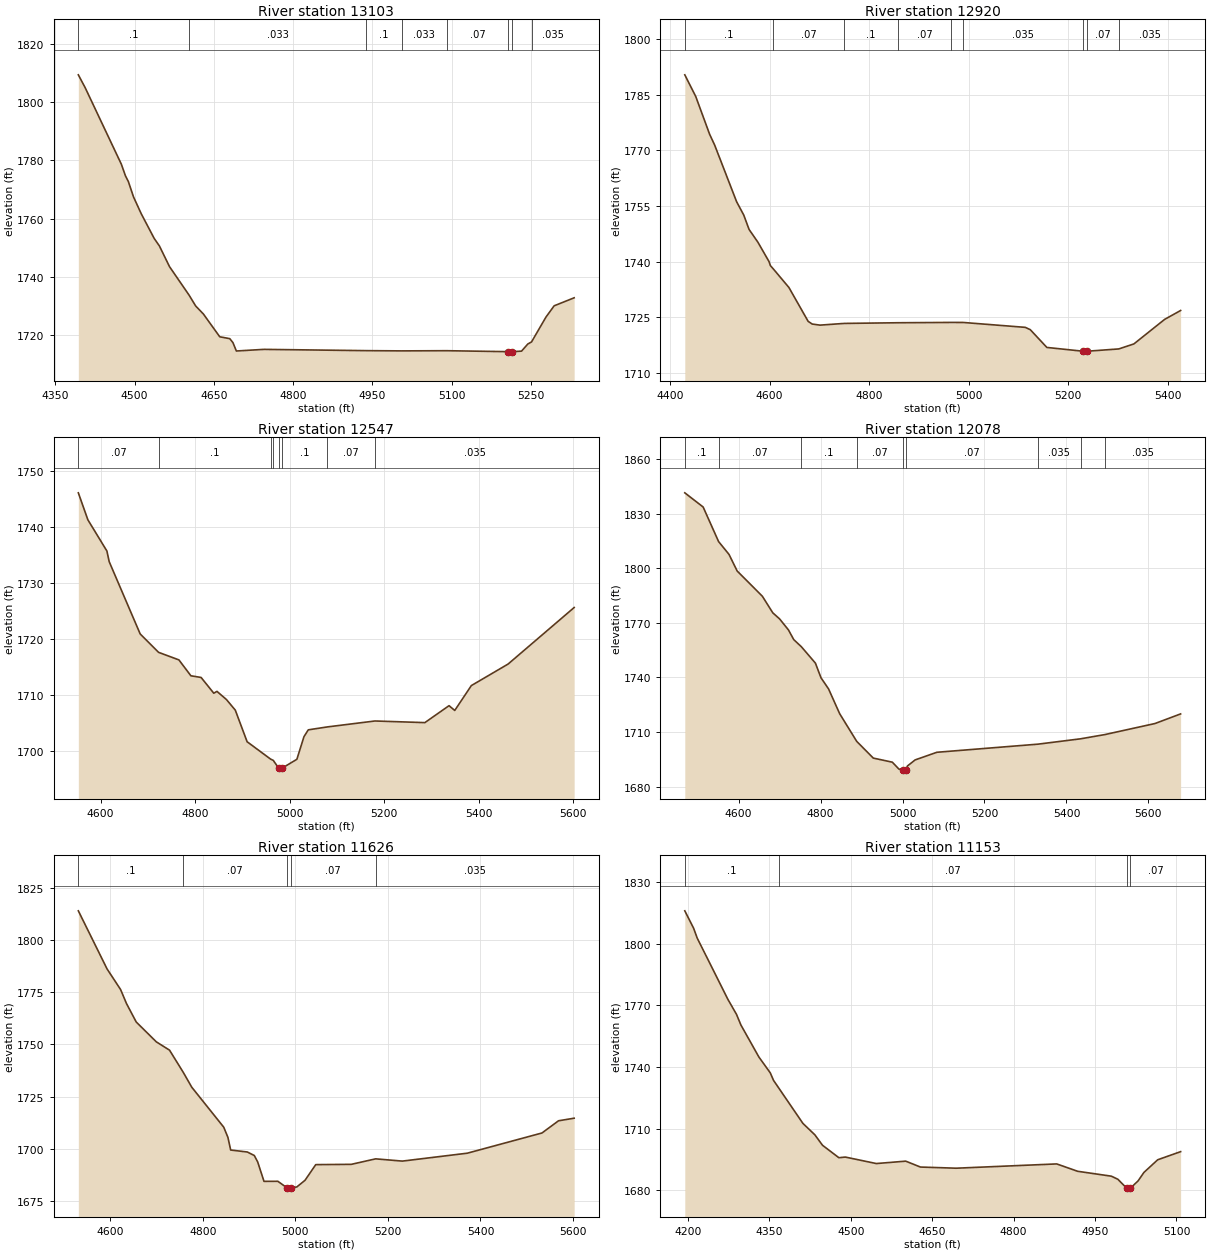
Type RM Length L Ch R = 1 ,13103   ,183,183,183
BEGIN DESCRIPTION:
Second Creek 26.0
END DESCRIPTION:
XS GIS Cut Line= 3
      1943824.98     13919675.02       1943448.8     13920159.17
      1943374.99     13920475.04
#Sta/Elev= 30
  4393.8 1809.38  4406.7 1804.98  4475.1  1778.7    4483 1774.66  4488.4 1772.73
  4498.2 1767.43  4512.9 1761.62  4537.3 1753.19  4547.1 1750.62  4566.2 1743.52
  4603.4 1733.68  4615.6 1730.03  4630.2 1727.27  4661.2 1719.43  4680.2 1718.79
  4686.2  1717.4  4692.6 1714.55  4744.8 1715.11  4938.4 1714.67  5005.3 1714.59
  5090.7 1714.65  5207.1 1714.32  5207.6 1713.82  5213.4 1714.32  5231.8  1714.5
  5243.7 1716.96  5250.7 1717.66    5278  1726.2  5293.5 1730.07  5331.3 1732.82
#Mann= 8 ,-1 , 0
  4393.8      .1       0  4603.4    .033       0  4938.4      .1       0
  5005.3    .033       0  5090.7     .07       0  5207.1     .05       0
  5213.4     .07       0  5250.7    .035       0
Bank Sta=5207.1,5213.4
XS Rating Curve= 0 ,0
Exp/Cntr=0.3,0.1

Type RM Length L Ch R = 1 ,12920   ,373,373,373
BEGIN DESCRIPTION:
Second Creek 25.1
END DESCRIPTION:
XS GIS Cut Line= 4
      1943743.41     13919568.63      1943529.88     13919706.65
      1943277.28     13920224.88      1943253.84     13920388.95
#Sta/Elev= 30
  4429.4 1790.33  4451.4  1784.5  4479.3 1774.32  4489.4 1771.42  4533.5 1756.17
  4547.9 1752.56  4558.6 1748.69  4576.4 1745.24  4598.7 1740.03  4601.4 1738.96
  4607.6 1738.01  4638.6 1733.07  4677.3 1723.94  4685.5 1723.21  4701.2 1722.92
  4749.8 1723.38  4857.5 1723.56  4965.3 1723.65  4988.8 1723.64  5113.7 1722.32
  5123.7  1721.7  5157.1 1716.91  5230.7 1715.88  5231.2 1715.38  5236.5 1715.38
    5237 1715.88  5301.6 1716.51    5332 1717.86  5393.8 1724.47  5425.9 1726.86
#Mann= 9 ,-1 , 0
  4429.4      .1       0  4607.6     .07       0  4749.8      .1       0
  4857.5     .07       0  4965.3      .1       0  4988.8    .035       0
  5230.7    .035       0    5237     .07       0  5301.6    .035       0
Bank Sta=5230.7,5237
XS Rating Curve= 0 ,0
Exp/Cntr=0.3,0.1

Type RM Length L Ch R = 1 ,12547   ,469,469,469
BEGIN DESCRIPTION:
Second Creek 25.0
END DESCRIPTION:
XS GIS Cut Line= 3
      1943575.01       13919575.        1943175.       13919775.
        1943225.       13920375.
#Sta/Elev= 30
  4552.8 1746.04    4573 1741.23  4613.3 1735.66  4618.1 1733.77  4683.7 1720.88
  4722.6  1717.6  4765.7 1716.25    4791 1713.42  4812.6 1713.12  4839.5 1710.31
  4846.2 1710.64  4866.3 1709.18    4885 1707.29    4910 1701.66  4959.6 1698.57
  4965.3 1698.34  4977.1 1696.92  4977.6 1696.42  4983.5 1696.92  5015.3 1698.53
  5030.3 1702.56  5039.4 1703.78  5079.6  1704.3  5180.6 1705.36  5286.2 1705.07
  5337.3 1708.09  5349.4 1707.24  5384.5 1711.67  5462.3 1715.51  5602.1 1725.59
#Mann= 8 ,-1 , 0
  4552.8     .07       0  4722.6      .1       0  4959.6     .07       0
  4965.3      .1       0  4977.1     .05       0  4983.5      .1       0
  5079.6     .07       0  5180.6    .035       0
Bank Sta=4977.1,4983.5
XS Rating Curve= 0 ,0
Exp/Cntr=0.3,0.1

Type RM Length L Ch R = 1 ,12078   ,452,452,452
BEGIN DESCRIPTION:
Second Creek 24.0
END DESCRIPTION:
XS GIS Cut Line= 3
      1942374.98     13919324.98        1942725.       13919725.
      1942931.07     13920371.62
#Sta/Elev= 30
  4468.5 1841.41  4513.3 1833.61    4551 1814.62  4576.4 1807.59  4596.3 1798.47
  4657.8  1784.6  4683.3 1775.48    4700 1772.13  4721.6 1766.06  4734.4 1760.78
  4753.1 1756.84  4787.3 1747.86    4801 1739.78  4819.4 1733.69  4846.5 1720.07
  4888.2 1704.85  4928.5 1695.69    4975 1693.44    4991 1689.67    5002 1689.02
  5002.5 1688.52  5008.9 1689.02  5011.8 1691.32  5030.7 1694.68  5083.7 1698.87
  5330.4 1703.33  5434.7 1706.28  5493.4 1708.58  5616.3 1714.68  5678.7 1719.96
#Mann= 9 ,-1 , 0
  4468.5      .1       0    4551     .07       0  4753.1      .1       0
  4888.2     .07       0    5002     .05       0  5008.9     .07       0
  5330.4    .035       0  5434.7     .07       0  5493.4    .035       0
Bank Sta=5002,5008.9
XS Rating Curve= 0 ,0
Exp/Cntr=0.3,0.1

Type RM Length L Ch R = 1 ,11626   ,473,473,473
BEGIN DESCRIPTION:
Second Creek 23.0
END DESCRIPTION:
XS GIS Cut Line= 3
      1942311.59     13919401.17        1942325.       13919875.
      1942587.57     13920411.58
#Sta/Elev= 30
    4531 1814.06    4593 1786.25  4622.3 1776.35  4635.1 1769.61  4656.1 1760.78
  4699.5 1751.28  4728.1 1747.28  4757.7 1736.67  4776.1 1729.54  4845.2 1710.37
  4854.2 1705.51  4860.2 1699.43  4896.2 1698.48  4911.2 1696.81  4918.5 1693.75
  4932.2 1684.42  4962.2 1684.44  4982.7 1681.19  4983.2 1680.69  4989.8 1681.19
  5003.2 1681.75  5020.8 1684.91    5044 1692.43    5121 1692.57  5173.4  1695.2
  5231.2 1694.12  5371.5 1697.91  5532.9  1707.6  5568.6 1713.44  5602.4 1714.68
#Mann= 5 ,-1 , 0
    4531      .1       0  4757.7     .07       0  4982.7     .05       0
  4989.8     .07       0  5173.4    .035       0
Bank Sta=4982.7,4989.8
XS Rating Curve= 0 ,0
Exp/Cntr=0.3,0.1

Type RM Length L Ch R = 1 ,11153   ,157,157,157
BEGIN DESCRIPTION:
Second Creek 22.0
END DESCRIPTION:
XS GIS Cut Line= 3
        1942125.     13919374.97        1942075.       13920175.
        1942125.       13920275.
#Sta/Elev= 30
  4194.2 1816.04  4210.5 1807.54  4217.1 1802.76  4273.6 1772.98  4289.5 1765.64
  4297.6 1760.49  4330.7 1744.93  4351.7  1737.2  4357.7 1733.55    4368 1729.57
  4411.8 1712.63  4433.7 1707.11  4447.9    1702    4478 1695.95    4490 1696.25
  4547.1  1693.1  4601.2 1694.27  4628.3  1691.4  4694.4 1690.84  4879.4 1692.92
  4917.9 1689.34    4980 1686.96    4992 1685.46  5008.1 1681.16  5008.6 1680.66
  5015.2 1681.16  5029.2 1684.65  5039.9 1688.75  5065.3 1694.93  5107.6 1698.89
#Mann= 4 ,-1 , 0
  4194.2      .1       0    4368     .07       0  5008.1     .05       0
  5015.2     .07       0
Bank Sta=5008.1,5015.2
XS Rating Curve= 0 ,0
Exp/Cntr=0.3,0.1