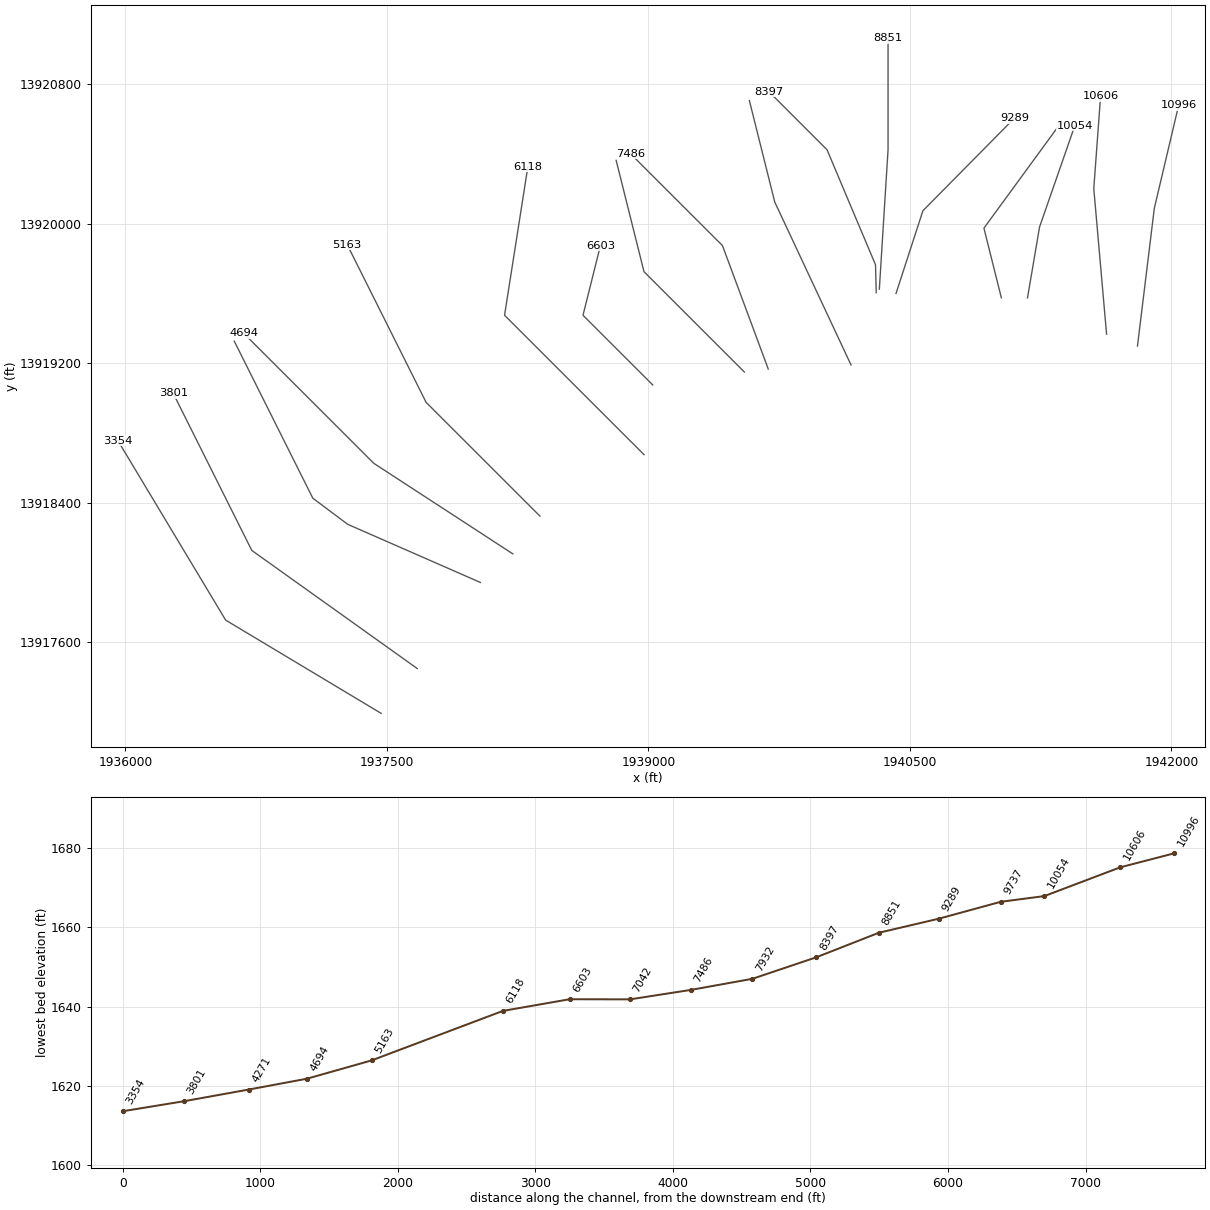
HEC-RAS study Second Creek.prj: Second Creek Base Level Engineering

--- Second Creek.g01 (geometry) --- (continued)

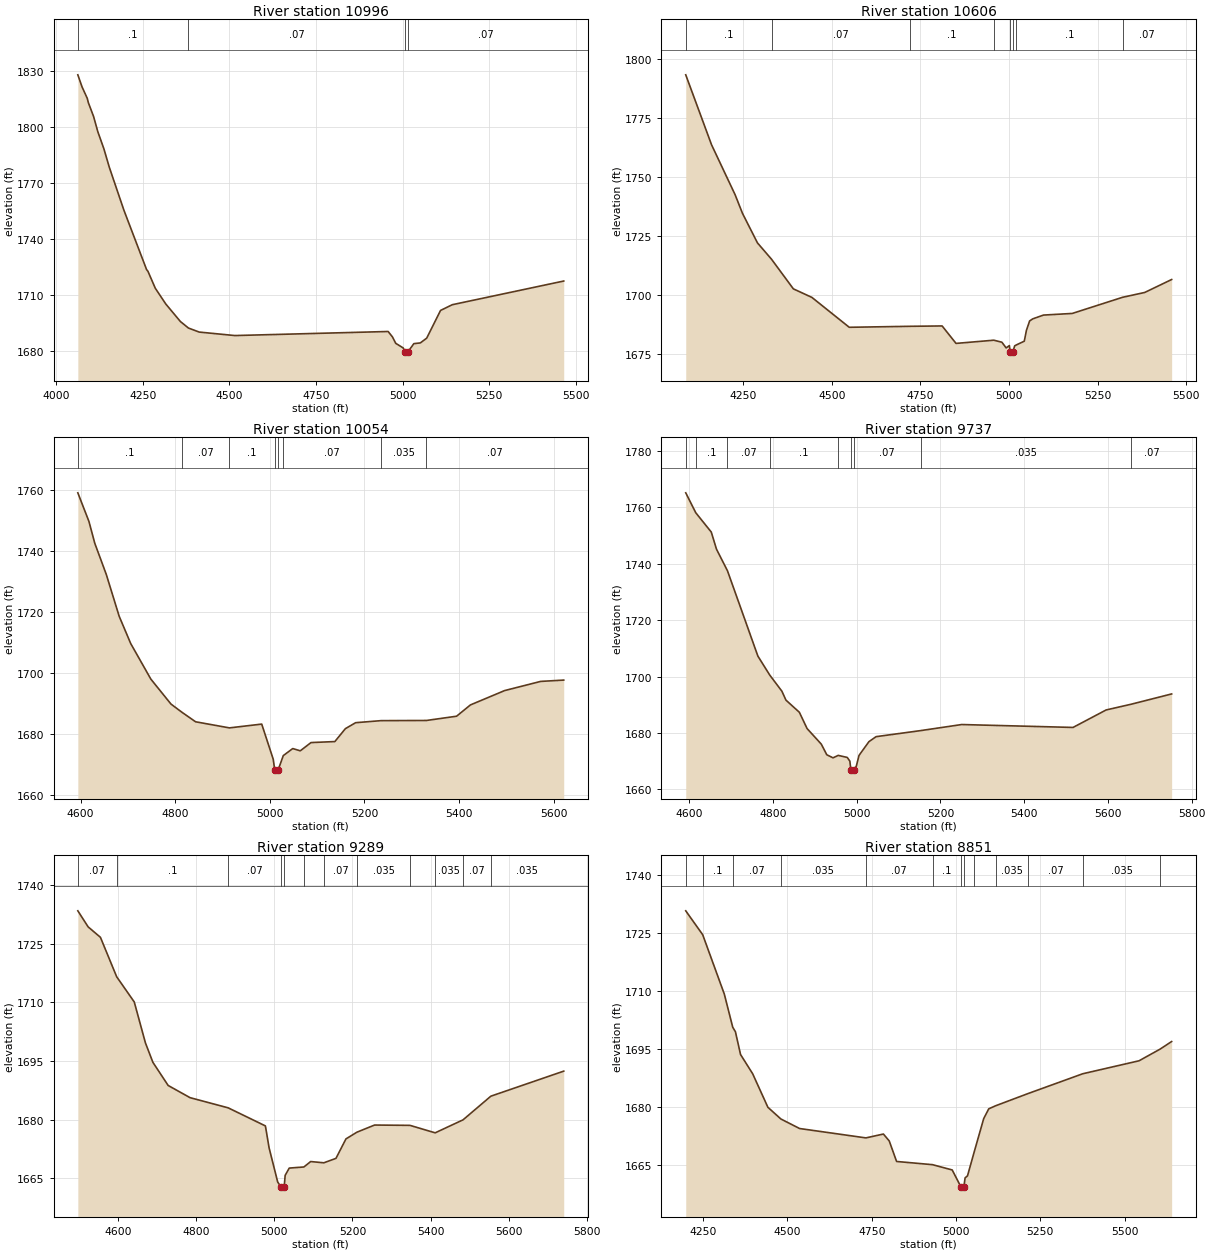
Type RM Length L Ch R = 1 ,10996   ,390,390,390
BEGIN DESCRIPTION:
Second Creek 21.1
END DESCRIPTION:
XS GIS Cut Line= 3
       1941805.8     13919298.14      1941902.54     13920089.27
      1942041.85     13920679.42
#Sta/Elev= 30
    4062 1828.09  4074.1 1821.65  4089.3 1815.44  4092.3 1813.18  4107.4 1805.79
  4119.5 1797.71  4137.6 1788.19  4152.7  1778.6    4195 1755.48  4260.5 1723.59
  4264.6 1722.61  4285.7 1713.57  4315.9 1705.13  4358.2  1695.7  4381.5 1692.19
  4412.6 1690.03  4515.4 1688.16  4958.2 1690.34  4970.7 1687.44  4980.2 1683.99
  5001.8 1681.51  5007.5 1679.23    5008 1678.73  5014.6 1679.23  5032.6 1683.83
  5051.1  1684.2  5069.6 1686.77  5109.6 1701.64  5143.6 1704.72  5465.4 1717.42
#Mann= 4 ,-1 , 0
    4062      .1       0  4381.5     .07       0  5007.5     .05       0
  5014.6     .07       0
Bank Sta=5007.5,5014.6
XS Rating Curve= 0 ,0
Exp/Cntr=0.3,0.1

Type RM Length L Ch R = 1 ,10606   ,552,552,552
BEGIN DESCRIPTION:
Second Creek 21.2
END DESCRIPTION:
XS GIS Cut Line= 3
      1941628.62     13919366.64      1941555.22     13920202.02
      1941594.26     13920732.79
#Sta/Elev= 30
    4088 1793.17  4160.8 1763.52  4227.1 1742.41  4248.2 1734.42  4290.3 1721.94
  4330.1 1714.99  4391.6 1702.45  4443.9 1698.83  4549.3 1686.16  4721.2 1686.58
  4811.3 1686.73  4850.5 1679.33  4957.1 1680.69  4979.9 1679.83  4991.9 1677.42
    5001 1678.41  5003.2 1675.71  5003.7 1675.21  5010.7 1675.71    5016  1678.3
    5021 1678.71  5043.1 1680.27  5049.1 1684.84  5058.1 1688.85  5067.1 1689.74
  5097.2 1691.34  5178.4 1692.03  5320.3 1698.87    5383 1700.93  5458.8 1706.41
#Mann= 8 ,-1 , 0
    4088      .1       0  4330.1     .07       0  4721.2      .1       0
  4957.1     .07       0  5003.2     .05       0  5010.7     .07       0
    5021      .1       0  5320.3     .07       0
Bank Sta=5003.2,5010.7
XS Rating Curve= 0 ,0
Exp/Cntr=0.3,0.1

Type RM Length L Ch R = 1 ,10054   ,317,317,317
BEGIN DESCRIPTION:
Second Creek 21.0
END DESCRIPTION:
XS GIS Cut Line= 3
        1941175.     13919574.98      1941244.19     13919982.05
      1941445.98     13920562.15
#Sta/Elev= 30
  4594.3 1759.06  4617.8 1749.68  4630.1 1742.56  4654.4 1732.36  4681.7 1718.64
  4706.1  1709.7  4748.7 1698.05  4791.2 1689.89  4814.4  1687.2  4843.2 1684.09
  4914.7 1682.09    4983 1683.33  5007.4  1671.8  5010.4 1668.43  5010.9 1667.93
    5018 1668.43  5028.6 1673.02  5048.6 1675.32  5064.5 1674.58  5087.2 1677.28
  5137.6 1677.61  5159.8 1681.83  5181.5 1683.79  5235.3 1684.46  5331.3 1684.52
  5394.9 1685.91  5424.2 1689.61  5496.5 1694.31  5572.7 1697.31  5621.4 1697.74
#Mann= 8 ,-1 , 0
  4594.3      .1       0  4814.4     .07       0  4914.7      .1       0
  5010.4     .05       0    5018      .1       0  5028.6     .07       0
  5235.3    .035       0  5331.3     .07       0
Bank Sta=5010.4,5018
XS Rating Curve= 0 ,0
Exp/Cntr=0.3,0.1

Type RM Length L Ch R = 1 ,9737    ,448,448,448
BEGIN DESCRIPTION:
Second Creek 20.0
END DESCRIPTION:
XS GIS Cut Line= 3
      1941024.99     13919575.03        1940925.       13919975.
      1941366.14     13920579.09
#Sta/Elev= 30
  4591.9 1765.17  4615.8 1758.12  4652.9 1751.25  4665.3 1745.19  4691.5 1737.54
  4764.2 1707.27  4792.5 1700.55  4821.5 1694.83  4831.2 1691.66  4863.2 1687.36
  4881.7 1681.58  4915.7 1676.04  4928.7  1672.3  4943.6  1671.2    4956 1672.07
  4977.6 1671.34  4983.8 1670.02  4986.1 1666.99  4986.6 1666.49  4993.7 1666.99
  4999.2 1668.23  5005.7 1672.07  5029.3 1676.93  5046.4 1678.71  5152.5 1680.85
  5250.8 1683.01  5516.7 1681.98  5595.8 1688.18  5656.1 1690.23  5752.2 1693.86
#Mann= 9 ,-1 , 0
  4591.9     .07       0  4615.8      .1       0  4691.5     .07       0
  4792.5      .1       0    4956     .07       0  4986.1     .05       0
  4993.7     .07       0  5152.5    .035       0  5656.1     .07       0
Bank Sta=4986.1,4993.7
XS Rating Curve= 0 ,0
Exp/Cntr=0.3,0.1

Type RM Length L Ch R = 1 ,9289    ,438,438,438
BEGIN DESCRIPTION:
Second Creek 19.0
END DESCRIPTION:
XS GIS Cut Line= 3
      1940420.74     13919600.11        1940575.       13920075.
        1941099.     13920605.54
#Sta/Elev= 30
  4496.3 1733.37  4522.7 1729.27  4554.2  1726.6  4595.8 1716.52  4640.9 1710.07
  4669.5 1699.61  4688.6 1694.65  4727.7 1688.73  4783.8 1685.61  4881.5 1683.01
  4976.9 1678.39  4986.4 1672.76  5008.4 1664.05  5017.2 1662.73  5017.7 1662.23
    5025 1662.73  5027.5 1665.74    5038 1667.61  5075.5 1667.89  5092.9 1669.28
  5126.5 1668.96  5157.7 1670.09  5183.3 1675.07  5211.5 1676.79  5256.6 1678.61
  5347.4 1678.53  5411.9 1676.62  5483.3 1679.94  5554.6 1685.99  5741.3 1692.39
#Mann= 12 ,-1 , 0
  4496.3     .07       0  4595.8      .1       0  4881.5     .07       0
  5017.2     .05       0    5025     .07       0  5075.5      .1       0
  5126.5     .07       0  5211.5    .035       0  5347.4     .07       0
  5411.9    .035       0  5483.3     .07       0  5554.6    .035       0
Bank Sta=5017.2,5025
XS Rating Curve= 0 ,0
Exp/Cntr=0.3,0.1

Type RM Length L Ch R = 1 ,8851    ,454,454,454
BEGIN DESCRIPTION:
Second Creek 18.0
END DESCRIPTION:
XS GIS Cut Line= 4
        1940325.     13919625.03        1940375.       13920425.
        1940375.       13920525.        1940375.     13921064.67
#Sta/Elev= 30
  4198.4  1730.8  4248.7 1724.61  4312.8 1709.22  4337.8 1700.62  4345.8 1699.45
  4360.9 1693.56  4396.9 1688.57    4442 1679.88  4480.6 1676.84  4536.1 1674.37
  4732.8 1671.94  4784.7 1672.94    4802 1671.14  4823.8 1665.83  4930.3    1665
  4988.7 1663.63  5015.1 1659.16  5015.6 1658.66  5023.1 1659.16    5027 1661.58
  5034.1  1662.1  5053.2 1668.06  5082.1 1676.93  5097.1 1679.47  5117.8 1680.28
  5213.6 1683.43  5376.1 1688.57    5543 1691.93  5605.3 1694.95  5639.6 1696.92
#Mann= 13 ,-1 , 0
  4198.4     .07       0  4248.7      .1       0  4337.8     .07       0
  4480.6    .035       0  4732.8     .07       0  4930.3      .1       0
  5015.1     .05       0  5023.1      .1       0  5053.2     .07       0
  5117.8    .035       0  5213.6     .07       0  5376.1    .035       0
  5605.3     .07       0
Bank Sta=5015.1,5023.1
XS Rating Curve= 0 ,0
Exp/Cntr=0.3,0.1

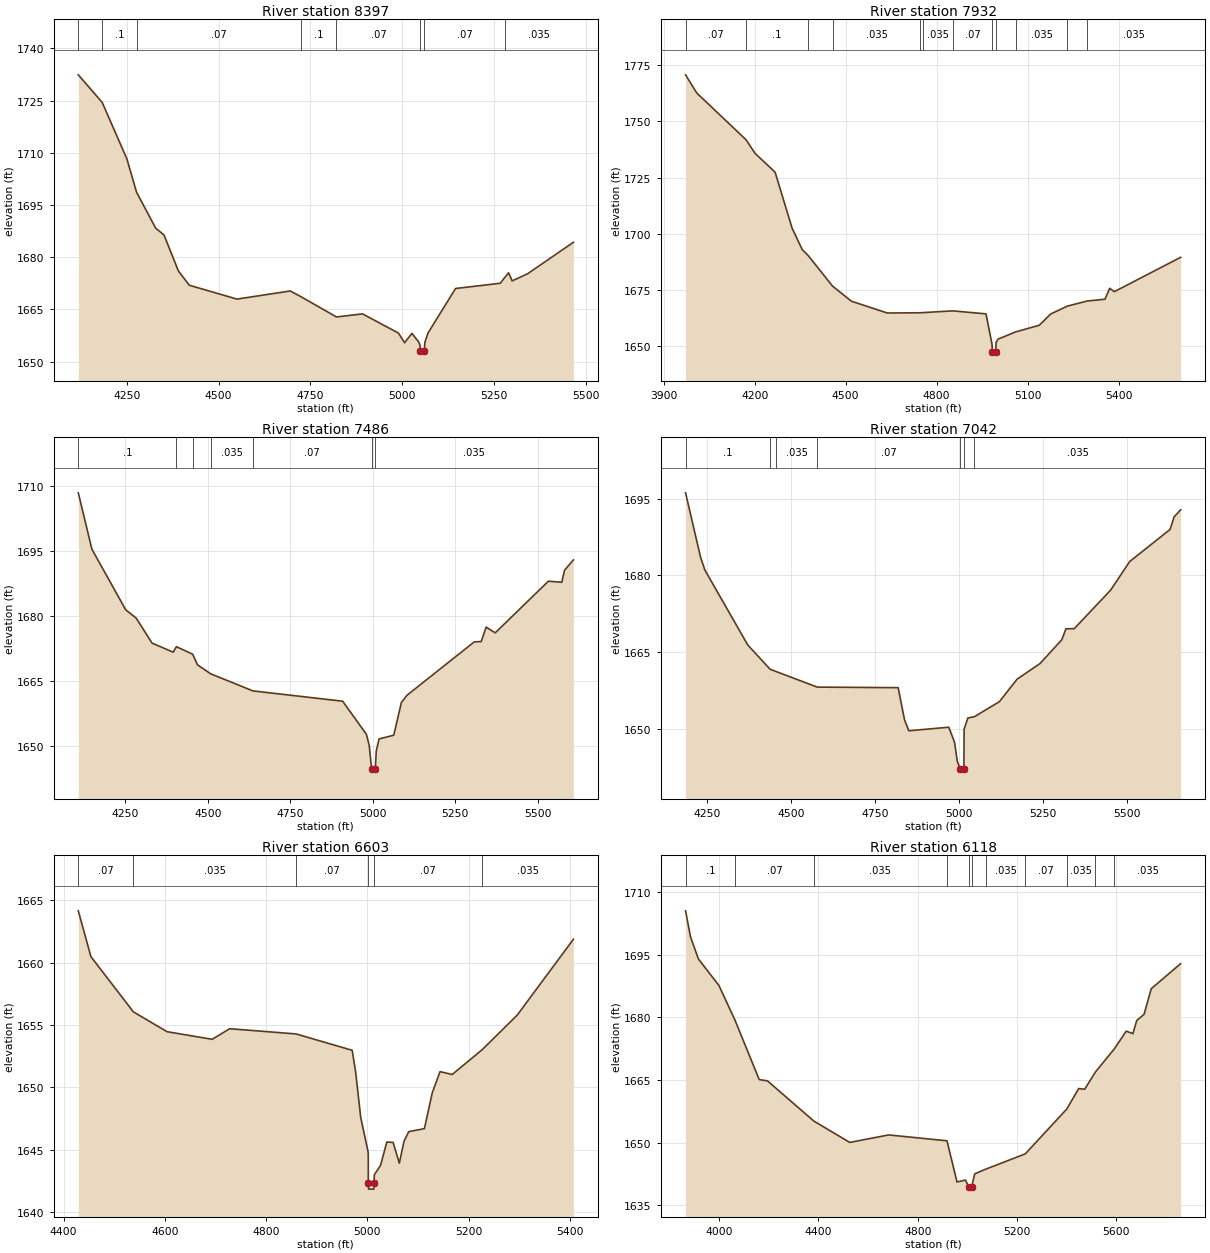
Type RM Length L Ch R = 1 ,8397    ,465,465,465
BEGIN DESCRIPTION:
Second Creek 17.0
END DESCRIPTION:
XS GIS Cut Line= 5
      1940307.19     13919604.63        1940303.     13919764.78
        1940025.       13920425.        1939875.       13920575.
      1939692.07     13920757.93
#Sta/Elev= 30
  4118.4 1732.42  4183.5 1724.49  4250.7 1708.25  4276.9 1698.71    4329 1688.37
  4351.7  1686.4  4390.8 1676.08  4420.5 1671.97  4550.3 1667.98  4695.1 1670.32
  4725.7  1668.6    4821 1662.85  4892.1 1663.73  4989.7 1658.22  5006.4 1655.44
  5026.3 1658.14  5044.6  1655.7  5048.8 1654.61    5049 1652.96  5049.5 1652.46
  5060.1 1652.96  5061.5  1655.5    5070 1658.21  5145.1 1671.03  5266.7 1672.53
    5280 1674.31  5289.4 1675.55  5299.1 1673.21  5341.6 1675.29  5465.8 1684.31
#Mann= 8 ,-1 , 0
  4118.4     .07       0  4183.5      .1       0  4276.9     .07       0
  4725.7      .1       0    4821     .07       0    5049     .05       0
  5060.1     .07       0    5280    .035       0
Bank Sta=5049,5060.1
XS Rating Curve= 0 ,0
Exp/Cntr=0.3,0.1

Type RM Length L Ch R = 1 ,7932    ,446,446,446
BEGIN DESCRIPTION:
Second Creek 16.0
END DESCRIPTION:
XS GIS Cut Line= 4
      1940162.63     13919189.66        1939725.       13920125.
        1939675.       13920325.      1939579.42     13920707.32
#Sta/Elev= 30
  3971.9  1770.7  4008.9 1762.62  4171.4 1741.85  4201.5 1735.73  4267.3 1727.42
  4323.3 1702.54  4356.7 1693.02    4377 1690.27  4456.8 1676.78    4519 1670.09
    4637 1664.85  4746.5 1664.94  4755.1 1665.02  4853.2 1665.79  4962.8 1664.46
  4982.7 1650.95  4983.8 1647.51  4984.3 1647.01  4994.9 1647.51  4995.9 1651.73
  5002.4 1653.22  5060.1 1656.42  5138.8 1659.42  5175.9 1664.39  5231.4 1667.91
  5296.7 1670.17  5355.2 1670.97  5370.7 1675.82  5386.1 1674.33  5604.8  1689.6
#Mann= 12 ,-1 , 0
  3971.9     .07       0  4171.4      .1       0    4377     .07       0
  4456.8    .035       0  4746.5     .07       0  4755.1    .035       0
  4853.2     .07       0  4983.8     .05       0  4994.9     .07       0
  5060.1    .035       0  5231.4     .07       0  5296.7    .035       0
Bank Sta=4983.8,4994.9
XS Rating Curve= 0 ,0
Exp/Cntr=0.3,0.1

Type RM Length L Ch R = 1 ,7486    ,444,444,444
BEGIN DESCRIPTION:
Second Creek 15.0
END DESCRIPTION:
XS GIS Cut Line= 5
      1939687.67     13919166.54        1939425.       13919875.
        1939325.       13919975.        1939225.       13920075.
       1938898.4      13920401.6
#Sta/Elev= 30
  4107.6 1708.53  4148.8  1695.5  4251.2 1681.51  4283.2 1679.56  4331.2 1673.79
  4395.2  1671.7  4404.9 1672.97  4454.2 1671.24  4468.8 1668.78  4508.6 1666.71
  4636.7 1662.75  4908.7 1660.37  4980.7 1652.71  4989.2 1650.16  4996.4 1644.71
  4996.9 1644.21  5007.6 1644.71  5010.5 1648.82    5019 1651.65  5063.5 1652.51
  5086.7 1660.09  5103.9 1661.76  5307.5 1674.08  5328.6 1674.16  5343.5  1677.5
    5371 1676.17  5532.2 1688.11  5572.6 1687.85  5581.1 1690.64  5607.9 1693.03
#Mann= 7 ,-1 , 0
  4107.6      .1       0  4404.9     .07       0  4454.2      .1       0
  4508.6    .035       0  4636.7     .07       0  4996.4    .035       0
  5007.6    .035       0
Bank Sta=4996.4,5007.6
XS Rating Curve= 0 ,0
Exp/Cntr=0.3,0.1

Type RM Length L Ch R = 1 ,7042    ,439,439,439
BEGIN DESCRIPTION:
Second Creek 14.0
END DESCRIPTION:
XS GIS Cut Line= 5
      1939550.58     13919149.42        1939125.       13919575.
        1938975.       13919725.        1938925.       13919925.
      1938815.19     13920364.23
#Sta/Elev= 30
    4186 1696.13  4230.8 1683.51  4243.5 1681.06  4370.9 1666.45  4437.6 1661.69
  4455.3 1661.25  4577.8 1658.21  4818.5  1658.1  4837.6 1651.77  4850.2 1649.69
    4969 1650.38  4986.1 1647.49  4994.5 1643.72  5002.7 1642.31  5003.2 1641.81
    5014 1642.31  5014.6 1649.98  5025.8 1652.18  5045.3 1652.43  5119.7 1655.37
  5172.3 1659.76  5240.4  1662.8  5305.3 1667.45  5317.6 1669.59  5342.4 1669.62
  5450.6 1677.14  5507.3 1682.72  5627.3 1688.98  5639.6 1691.45  5658.9 1692.82
#Mann= 7 ,-1 , 0
    4186      .1       0  4437.6     .07       0  4455.3    .035       0
  4577.8     .07       0  5002.7     .05       0    5014     .07       0
  5045.3    .035       0
Bank Sta=5002.7,5014
XS Rating Curve= 0 ,0
Exp/Cntr=0.3,0.1

Type RM Length L Ch R = 1 ,6603    ,485,485,485
BEGIN DESCRIPTION:
Second Creek 13.0
END DESCRIPTION:
XS GIS Cut Line= 3
      1939024.98     13919075.02        1938625.       13919475.
      1938725.01     13919875.03
#Sta/Elev= 30
    4429 1664.15  4453.9 1660.48  4537.8 1656.05  4604.4 1654.46  4693.5 1653.85
  4728.1  1654.7  4859.2 1654.28    4970 1652.97  4976.6 1651.31  4986.9 1647.59
  5001.4 1644.84  5001.8 1644.63  5001.9 1642.34  5002.4 1641.84  5012.7 1641.84
  5013.2 1642.34  5013.8 1642.99  5026.1 1643.75  5038.5 1645.62  5050.9 1645.58
  5063.2 1643.92  5072.5 1645.69  5081.8 1646.45  5112.7 1646.69  5128.2 1649.56
  5143.6 1651.26  5167.6 1651.03  5227.2 1653.03  5296.2  1655.8    5407 1661.87
#Mann= 6 ,-1 , 0
    4429     .07       0  4537.8    .035       0  4859.2     .07       0
  5001.9     .05       0  5013.2     .07       0  5227.2    .035       0
Bank Sta=5001.9,5013.2
XS Rating Curve= 0 ,0
Exp/Cntr=0.3,0.1

Type RM Length L Ch R = 1 ,6118    ,955,955,955
BEGIN DESCRIPTION:
Second Creek 12.0
END DESCRIPTION:
XS GIS Cut Line= 3
      1938974.98     13918675.02        1938175.       13919475.
      1938308.82     13920328.43
#Sta/Elev= 30
  3864.4  1705.5  3884.3 1699.27  3916.2 1693.98  3998.8 1687.64  4063.7 1679.32
  4161.2 1665.11  4194.6  1664.8    4381  1655.2    4526 1650.07    4683 1651.86
  4917.9 1650.46  4958.3  1640.6  4992.3 1641.07  5005.8 1639.39  5006.3 1638.89
  5017.1 1639.39  5029.7 1642.55  5073.9 1643.66  5233.5 1647.33  5400.5 1658.05
  5448.7 1662.96  5472.8  1662.8  5516.4 1666.94  5592.4 1672.47  5640.1 1676.69
  5667.4 1676.12  5682.6 1679.26  5712.1 1680.72    5741 1686.85  5859.6 1692.86
#Mann= 11 ,-1 , 0
  3864.4      .1       0  4063.7     .07       0    4381    .035       0
  4917.9     .07       0  5005.8     .05       0  5017.1     .07       0
  5073.9    .035       0  5233.5     .07       0  5400.5    .035       0
  5516.4     .07       0  5592.4    .035       0
Bank Sta=5005.8,5017.1
XS Rating Curve= 0 ,0
Exp/Cntr=0.3,0.1

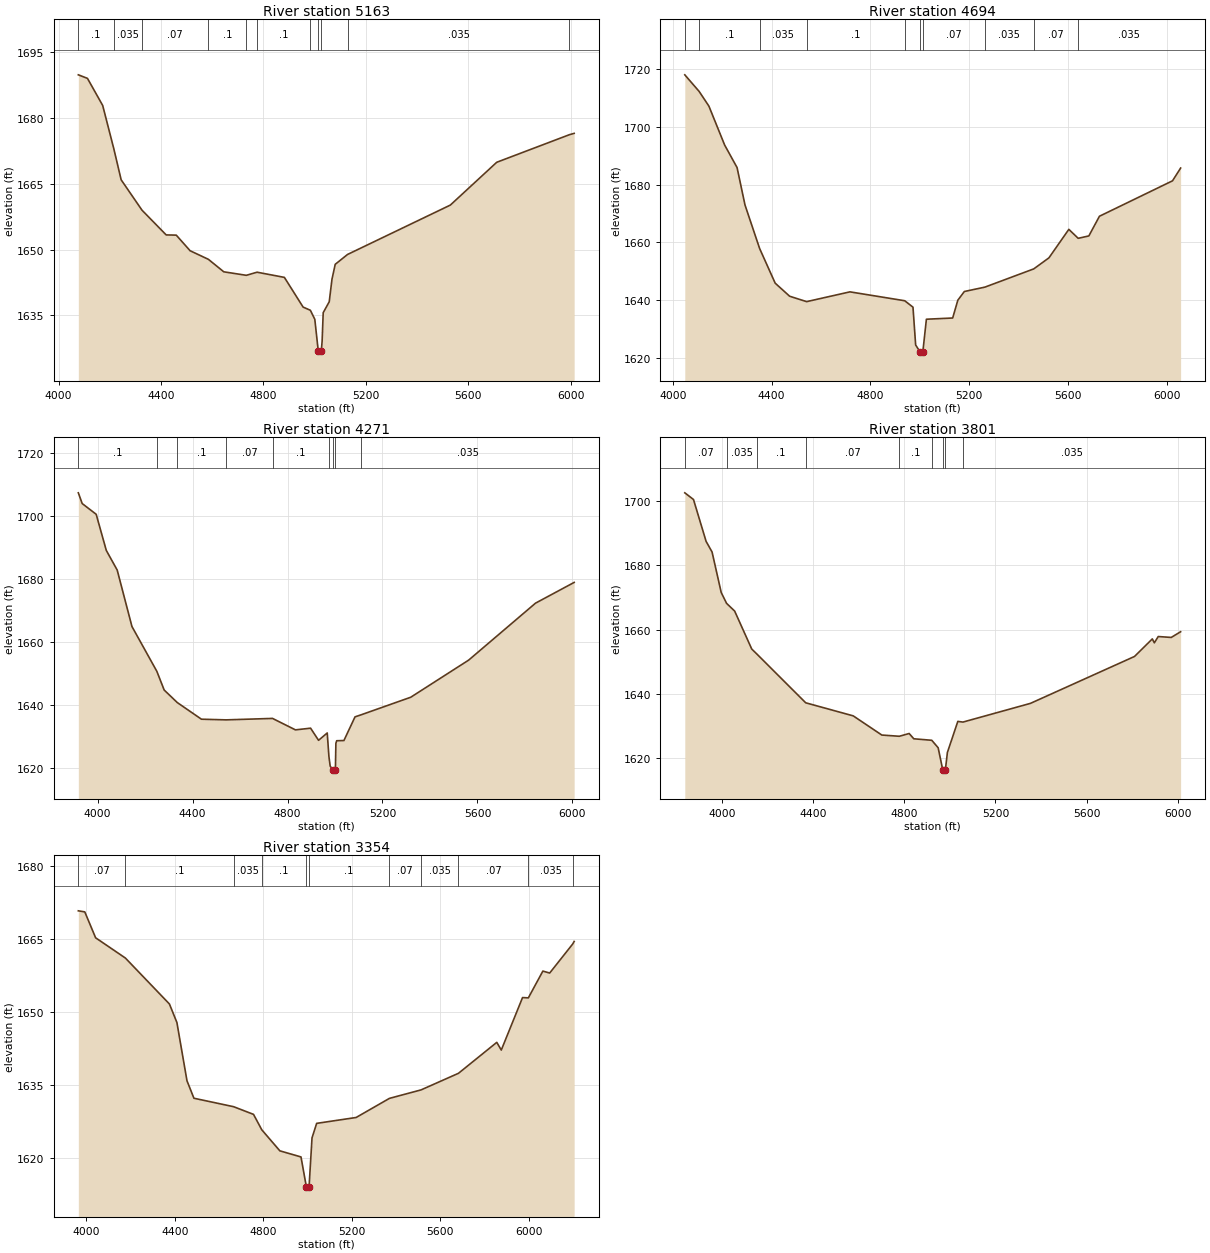
Type RM Length L Ch R = 1 ,5163    ,469,469,469
BEGIN DESCRIPTION:
Second Creek 11.0
END DESCRIPTION:
XS GIS Cut Line= 5
      1938377.69     13918322.31        1937825.       13918875.
        1937725.       13918975.        1937675.       13919075.
      1937272.04     13919880.92
#Sta/Elev= 30
  4077.2 1689.88  4112.9 1689.07  4172.3 1682.89  4215.9 1672.97  4244.4 1665.92
  4325.9 1658.98  4420.2 1653.34  4459.6 1653.29  4513.6 1649.73    4585 1647.77
  4645.1 1644.92  4733.2 1644.12    4775 1644.83  4881.7 1643.65  4954.8 1636.87
  4983.2 1636.14  5000.5 1634.08    5014 1626.86  5014.5 1626.36  5025.8 1626.86
    5029 1629.02  5033.3 1635.59  5056.8 1638.08  5067.6 1643.25  5080.2 1646.63
  5128.3 1648.88  5529.7 1660.15  5710.8 1669.92  5994.3 1676.21  6013.1 1676.52
#Mann= 11 ,-1 , 0
  4077.2      .1       0  4215.9    .035       0  4325.9     .07       0
    4585      .1       0  4733.2     .07       0    4775      .1       0
  4983.2     .07       0    5014     .05       0  5025.8     .07       0
  5128.3    .035       0  5994.3      .1       0
Bank Sta=5014,5025.8
XS Rating Curve= 0 ,0
Exp/Cntr=0.3,0.1

Type RM Length L Ch R = 1 ,4694    ,423,423,423
BEGIN DESCRIPTION:
Second Creek 10.0
END DESCRIPTION:
XS GIS Cut Line= 4
      1938222.51     13918105.25        1937425.       13918625.
        1937275.       13918775.      1936677.96     13919372.04
#Sta/Elev= 30
  4048.1 1717.95  4106.4 1712.19  4145.7 1707.14  4209.7 1693.65  4259.8  1685.9
    4292 1672.94  4351.2 1657.91  4414.2 1645.93  4472.8 1641.41  4541.6 1639.54
  4717.1 1642.92  4938.9 1639.85  4972.4 1637.63  4983.2 1624.55  5000.5 1622.24
    5001 1621.74  5012.4 1622.24  5026.7 1633.46  5133.2 1633.88    5154 1640.03
  5180.4 1643.04  5263.8 1644.56  5461.6 1650.86  5523.1 1654.68  5603.7 1664.53
  5641.6 1661.43  5684.8 1662.26  5727.7 1669.06  6023.7 1681.31  6056.5 1685.72
#Mann= 10 ,-1 , 0
  4048.1     .07       0  4106.4      .1       0  4351.2    .035       0
  4541.6      .1       0  4938.9     .07       0  5000.5     .05       0
  5012.4     .07       0  5263.8    .035       0  5461.6     .07       0
  5641.6    .035       0
Bank Sta=5000.5,5012.4
XS Rating Curve= 0 ,0
Exp/Cntr=0.3,0.1

Type RM Length L Ch R = 1 ,4271    ,470,470,470
BEGIN DESCRIPTION:
Second Creek 9.0
END DESCRIPTION:
XS GIS Cut Line= 5
      1938036.06     13917941.36        1937275.       13918275.
        1937075.       13918425.        1937025.       13918525.
      1936624.42     13919326.16
#Sta/Elev= 30
  3918.8 1707.44  3935.1 1704.03    3994 1700.62  4036.6 1689.14  4082.5  1682.9
  4144.7 1664.95  4249.5 1650.72  4280.4 1644.77  4335.7 1640.79  4437.3  1635.5
  4541.4 1635.29  4736.8 1635.75  4833.4 1632.11  4897.1 1632.65  4930.7 1628.79
  4967.2 1631.13  4974.3 1623.68  4979.6  1620.6  4989.7  1619.5  4990.2    1619
  5001.6  1619.5  5003.7 1627.84  5007.1 1628.66  5037.5 1628.72  5084.2 1636.24
    5110  1636.9    5319 1642.48  5562.8 1654.27  5844.6 1672.38  6007.3 1678.97
#Mann= 9 ,-1 , 0
  3918.8      .1       0  4249.5    .035       0  4335.7      .1       0
  4541.4     .07       0  4736.8      .1       0  4974.3     .07       0
  4989.7     .05       0  5001.6     .07       0    5110    .035       0
Bank Sta=4989.7,5001.6
XS Rating Curve= 0 ,0
Exp/Cntr=0.3,0.1

Type RM Length L Ch R = 1 ,3801    ,447,447,447
BEGIN DESCRIPTION:
Second Creek 8.0
END DESCRIPTION:
XS GIS Cut Line= 5
       1937674.1     13917447.07        1937075.       13917875.
        1936725.       13918125.        1936675.       13918225.
      1936274.37     13919026.26
#Sta/Elev= 30
  3838.1 1702.52  3876.2 1700.45  3931.5 1687.44  3957.6 1684.15  3997.8 1671.55
  4021.3 1668.18  4056.8 1665.77  4131.6 1653.99  4153.4 1652.48  4368.3 1637.28
  4576.6 1633.22    4702 1627.26  4778.6 1626.88  4821.9 1627.74  4842.1  1626.1
    4921 1625.63    4949 1623.31  4968.8 1616.55  4969.3 1616.05  4980.8 1616.55
  4989.5 1621.85  5035.2  1631.5  5057.7 1631.29  5353.6  1637.1    5810 1651.68
    5888 1657.13  5896.9 1655.92    5914 1657.87    5971 1657.59  6012.1 1659.36
#Mann= 9 ,-1 , 0
  3838.1     .07       0  4021.3    .035       0  4153.4      .1       0
  4368.3     .07       0  4778.6      .1       0    4921     .07       0
  4968.8     .05       0  4980.8     .07       0  5057.7    .035       0
Bank Sta=4968.8,4980.8
XS Rating Curve= 0 ,0
Exp/Cntr=0.3,0.1

Type RM Length L Ch R = 1 ,3354    ,468,468,468
BEGIN DESCRIPTION:
Second Creek 7.0
END DESCRIPTION:
XS GIS Cut Line= 5
      1937467.22     13917189.67        1936825.       13917575.
        1936575.       13917725.        1936425.       13917975.
      1935957.24     13918754.59
#Sta/Elev= 30
  3964.1 1670.77  3993.3 1670.55  4042.3 1665.22  4176.7 1661.06  4375.9  1651.6
  4409.7 1647.79  4455.2 1635.81  4486.6 1632.21    4666 1630.47    4756 1628.89
  4793.3 1625.72    4875 1621.39  4970.6 1620.13  4994.7 1614.01  4995.2 1613.51
  5007.1 1614.01  5020.4 1624.06  5041.4 1627.04  5219.8 1628.25  5370.2 1632.18
  5513.5 1633.93  5682.4 1637.34  5855.6 1643.71  5875.9 1642.12    5972 1652.92
  5998.2 1652.86  6063.9 1658.37  6094.7 1657.97  6198.8 1663.95  6205.3 1664.47
#Mann= 11 ,-1 , 0
  3964.1     .07       0  4176.7      .1       0    4666    .035       0
  4793.3      .1       0  4994.7     .05       0  5007.1      .1       0
  5370.2     .07       0  5513.5    .035       0  5682.4     .07       0
  5998.2    .035       0  6198.8      .1       0
Bank Sta=4994.7,5007.1
XS Rating Curve= 0 ,0
Exp/Cntr=0.3,0.1