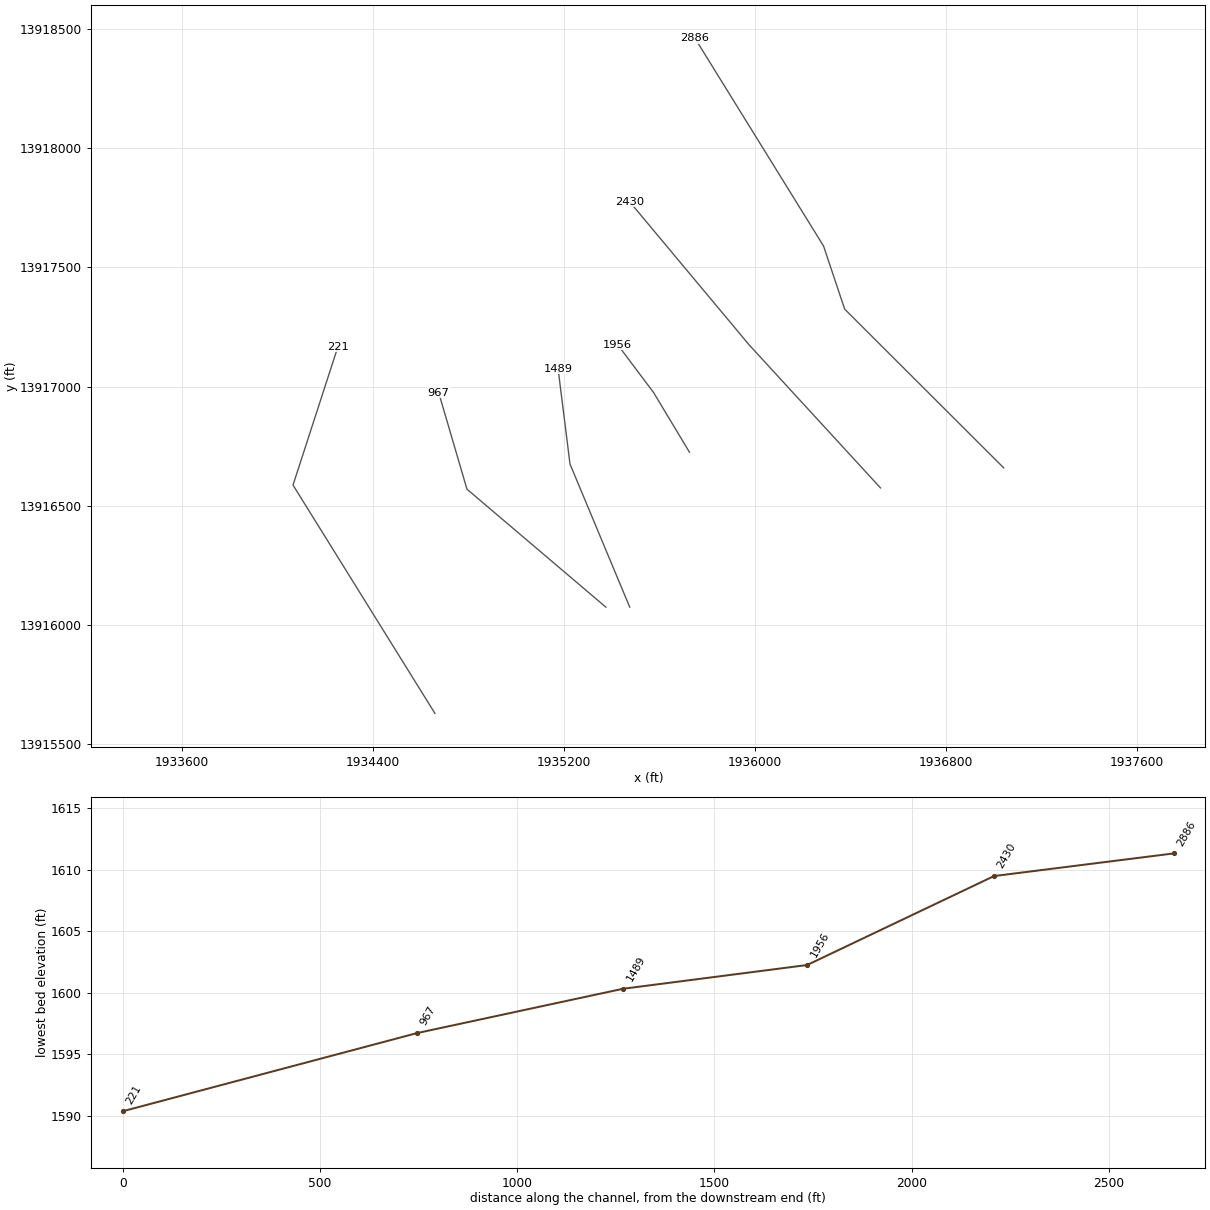
HEC-RAS study Second Creek.prj: Second Creek Base Level Engineering

--- Second Creek.g01 (geometry) --- (continued)

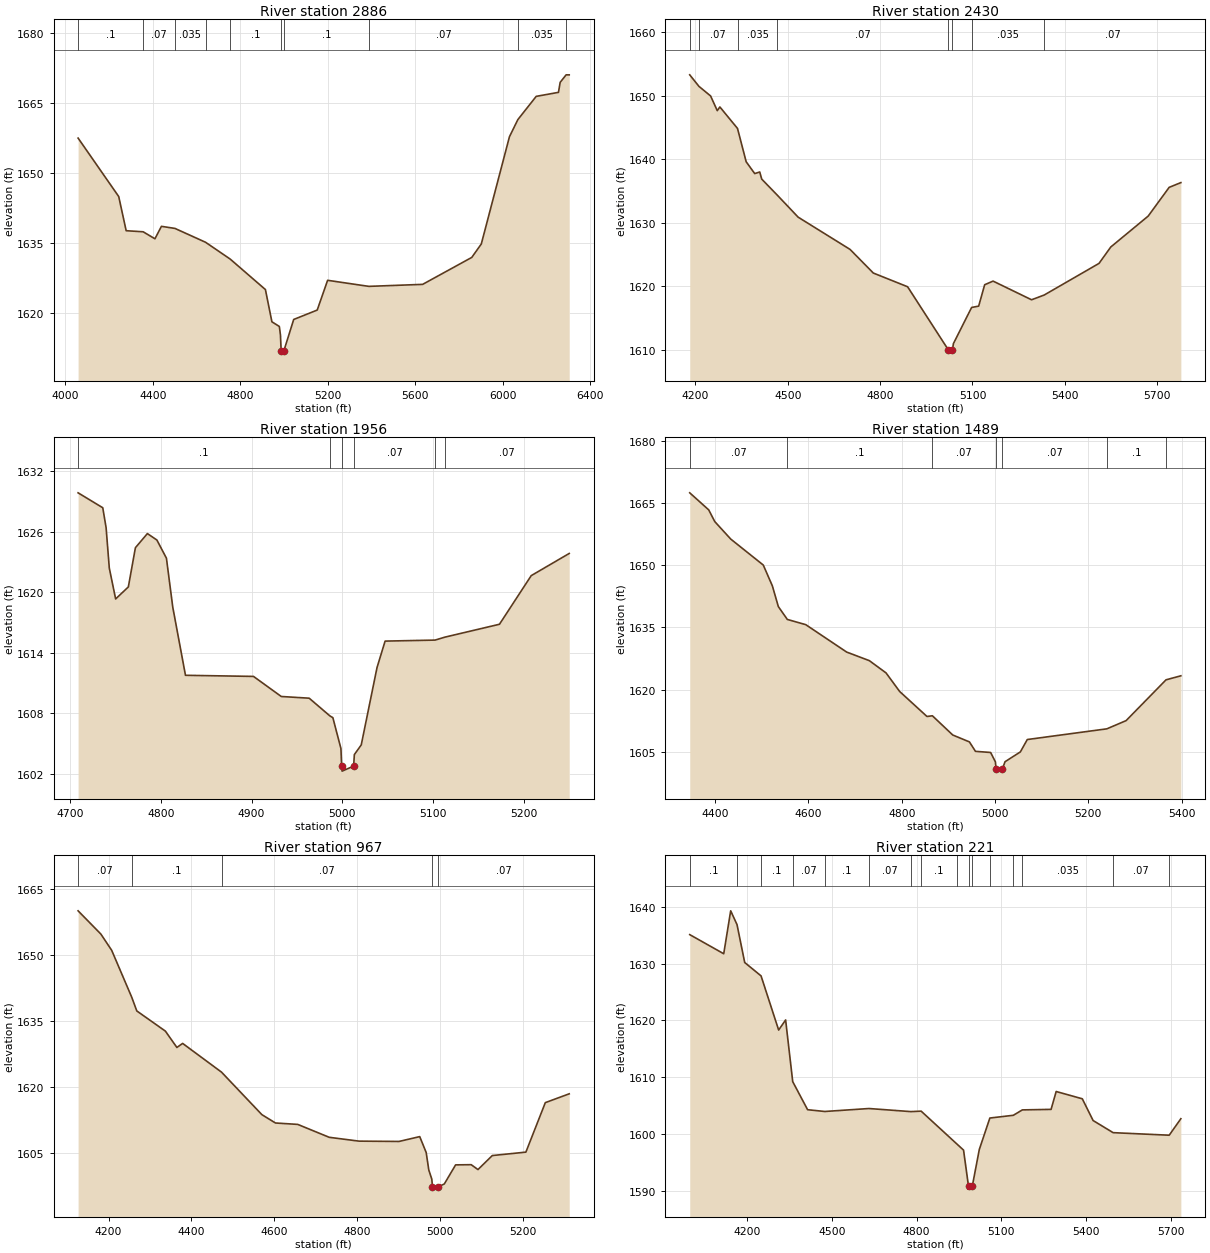
Type RM Length L Ch R = 1 ,2886    ,456,456,456
BEGIN DESCRIPTION:
Second Creek 6.0
END DESCRIPTION:
XS GIS Cut Line= 5
      1937040.79     13916659.21        1936475.       13917225.
        1936375.       13917325.      1936286.58     13917589.57
      1935748.33     13918460.79
#Sta/Elev= 30
  4058.7 1657.45  4244.4 1644.91  4278.4 1637.58  4355.9 1637.35  4409.9 1635.85
  4439.6 1638.52  4501.5 1638.07  4641.3  1635.1  4753.7  1631.5  4914.8 1624.96
  4944.5 1618.04  4978.4 1617.04  4983.6 1615.19  4986.7 1611.82  4987.2 1611.32
  4999.2 1611.82  5044.1 1618.54  5151.6 1620.56  5199.1 1626.94  5387.5 1625.64
  5633.4 1626.07  5857.9 1631.85  5901.5 1634.73  6030.1 1657.73  6068.5 1661.41
  6152.5  1666.4  6254.2 1667.26  6261.9  1669.4  6289.2 1671.02  6303.3 1671.01
#Mann= 10 ,-1 , 0
  4058.7      .1       0  4355.9     .07       0  4501.5    .035       0
  4641.3     .07       0  4753.7      .1       0  4986.7     .05       0
  4999.2      .1       0  5387.5     .07       0  6068.5    .035       0
  6289.2     .07       0
Bank Sta=4986.7,4999.2
XS Rating Curve= 0 ,0
Exp/Cntr=0.3,0.1

Type RM Length L Ch R = 1 ,2430    ,474,474,474
BEGIN DESCRIPTION:
Second Creek 5.0
END DESCRIPTION:
XS GIS Cut Line= 3
      1936524.98     13916575.02        1935975.       13917175.
      1935475.03     13917774.97
#Sta/Elev= 30
  4181.9  1653.3  4211.7 1651.49  4249.7 1649.97  4271.3 1647.66  4279.8 1648.24
    4337 1644.86  4365.2 1639.61  4392.9 1637.75  4409.2    1638  4415.7 1636.88
  4466.7 1634.33  4533.9 1630.89  4702.6 1625.81  4778.1 1622.09  4889.4 1619.93
  5021.9 1609.98  5022.4 1609.48  5034.9 1609.98  5038.2 1610.98  5097.3 1616.67
  5120.2 1616.88  5139.7 1620.25    5167 1620.82    5292 1617.88  5333.1 1618.63
  5511.1 1623.61  5549.2 1626.19  5670.8 1631.06  5738.8 1635.58  5776.8 1636.33
#Mann= 8 ,-1 , 0
  4181.9      .1       0  4211.7     .07       0    4337    .035       0
  4466.7     .07       0  5021.9     .05       0  5034.9     .07       0
  5097.3    .035       0  5333.1     .07       0
Bank Sta=5021.9,5034.9
XS Rating Curve= 0 ,0
Exp/Cntr=0.3,0.1

Type RM Length L Ch R = 1 ,1956    ,467,467,467
BEGIN DESCRIPTION:
Second Creek 4.0
END DESCRIPTION:
XS GIS Cut Line= 3
      1935724.99     13916725.02        1935575.       13916975.
      1935425.02     13917174.98
#Sta/Elev= 30
  4708.7 1629.84  4735.9 1628.36  4739.6 1626.37  4743.1 1622.38  4750.1 1619.32
  4764.1 1620.51  4771.9  1624.4  4785.1  1625.8  4795.6 1625.16  4806.1 1623.36
  4813.1  1618.5  4827.1 1611.75  4902.1 1611.64  4932.7 1609.65  4963.5 1609.48
  4986.4 1607.72  4989.6 1607.55  4998.5 1604.49  4999.3 1602.75  4999.8 1602.25
  5012.5 1602.75  5013.3 1603.89  5020.9 1604.85  5038.3 1612.52  5047.2 1615.14
  5102.3 1615.24    5113 1615.53  5173.3 1616.81  5208.3 1621.63  5250.2 1623.83
#Mann= 6 ,-1 , 0
  4708.7      .1       0  4986.4     .07       0  4999.3     .05       0
  5012.5     .07       0  5102.3      .1       0    5113     .07       0
Bank Sta=4999.3,5012.5
XS Rating Curve= 0 ,0
Exp/Cntr=0.3,0.1

Type RM Length L Ch R = 1 ,1489    ,522,522,522
BEGIN DESCRIPTION:
Second Creek 3.0
END DESCRIPTION:
XS GIS Cut Line= 3
        1935475.       13916075.        1935225.       13916675.
        1935175.     13917074.98
#Sta/Elev= 30
  4345.5 1667.44  4386.2 1663.33  4399.2  1660.5  4433.5 1656.28  4503.2 1650.02
  4522.7 1644.99  4535.5    1640  4554.8  1636.9  4594.2 1635.65  4681.9 1629.04
  4730.7 1626.96  4766.4 1624.01  4795.7 1619.52  4854.2  1613.5  4865.8 1613.67
  4909.5 1609.03  4945.2 1607.37  4958.2 1605.09  4990.7 1604.82  5000.9 1602.56
  5002.5 1600.82    5003 1600.32  5015.8 1600.82  5021.6 1602.59  5054.5 1604.96
  5069.3 1607.94  5239.9 1610.52  5281.2  1612.5  5366.8 1622.34  5398.6 1623.31
#Mann= 7 ,-1 , 0
  4345.5     .07       0  4554.8      .1       0  4865.8     .07       0
  5002.5     .05       0  5015.8     .07       0  5239.9      .1       0
  5366.8     .07       0
Bank Sta=5002.5,5015.8
XS Rating Curve= 0 ,0
Exp/Cntr=0.3,0.1

Type RM Length L Ch R = 1 ,967     ,746,746,746
BEGIN DESCRIPTION:
Second Creek 2.0
END DESCRIPTION:
XS GIS Cut Line= 3
      1935375.03     13916074.98       1934793.5     13916569.75
      1934675.01     13916974.95
#Sta/Elev= 30
  4126.5 1660.05  4181.5 1654.76  4207.6 1651.06  4255.9 1640.42  4268.2 1637.27
  4337.2 1632.68    4365 1628.96  4378.9 1629.88  4472.8 1623.34  4570.2 1613.67
    4603 1611.77  4656.7 1611.45  4732.9 1608.51  4804.8 1607.64  4901.3 1607.57
  4951.3 1608.67  4966.9 1605.05  4973.2 1601.07  4980.5 1598.99  4982.1 1597.22
  4982.6 1596.72  4995.4 1597.22  5010.7  1597.9  5037.9 1602.24  5075.6 1602.28
  5091.9 1601.17  5126.5 1604.36  5207.6 1605.14  5254.5  1616.4  5312.2 1618.41
#Mann= 5 ,-1 , 0
  4126.5     .07       0  4255.9      .1       0  4472.8     .07       0
  4982.1     .05       0  4995.4     .07       0
Bank Sta=4982.1,4995.4
XS Rating Curve= 0 ,0
Exp/Cntr=0.3,0.1

Type RM Length L Ch R = 1 ,221     ,0,0,0
BEGIN DESCRIPTION:
Second Creek 1.0
END DESCRIPTION:
XS GIS Cut Line= 3
      1934659.34     13915629.39       1934065.2     13916587.01
      1934253.12     13917167.07
#Sta/Elev= 30
  3997.8 1635.08    4118 1631.72  4142.6 1639.26    4165 1636.84  4192.2 1630.18
    4250 1627.83  4312.2 1618.32  4336.9 1620.09    4362 1609.25  4414.6 1604.32
  4475.6 1604.01  4631.5 1604.53  4779.4 1603.99  4816.1 1604.07    4942 1598.32
  4966.1 1597.22  4983.6 1590.87  4984.1 1590.37  4996.9 1590.87  5021.8 1597.34
  5059.1 1602.86  5142.1 1603.34    5174 1604.29  5275.6 1604.38  5293.6 1607.52
    5386 1606.24  5424.2 1602.42    5495 1600.29  5693.3 1599.84  5734.5 1602.74
#Mann= 16 ,-1 , 0
  3997.8      .1       0    4165     .07       0    4250      .1       0
    4362     .07       0  4475.6      .1       0  4631.5     .07       0
  4779.4    .035       0  4816.1      .1       0    4942     .07       0
  4983.6     .05       0  4996.9     .07       0  5059.1    .035       0
  5142.1     .07       0    5174    .035       0    5495     .07       0
  5693.3    .035       0
Bank Sta=4983.6,4996.9
XS Rating Curve= 0 ,0
Exp/Cntr=0.3,0.1

Chan Stop Cuts=-1
Use User Specified Reach Order=0
Composite Channel Slope=5