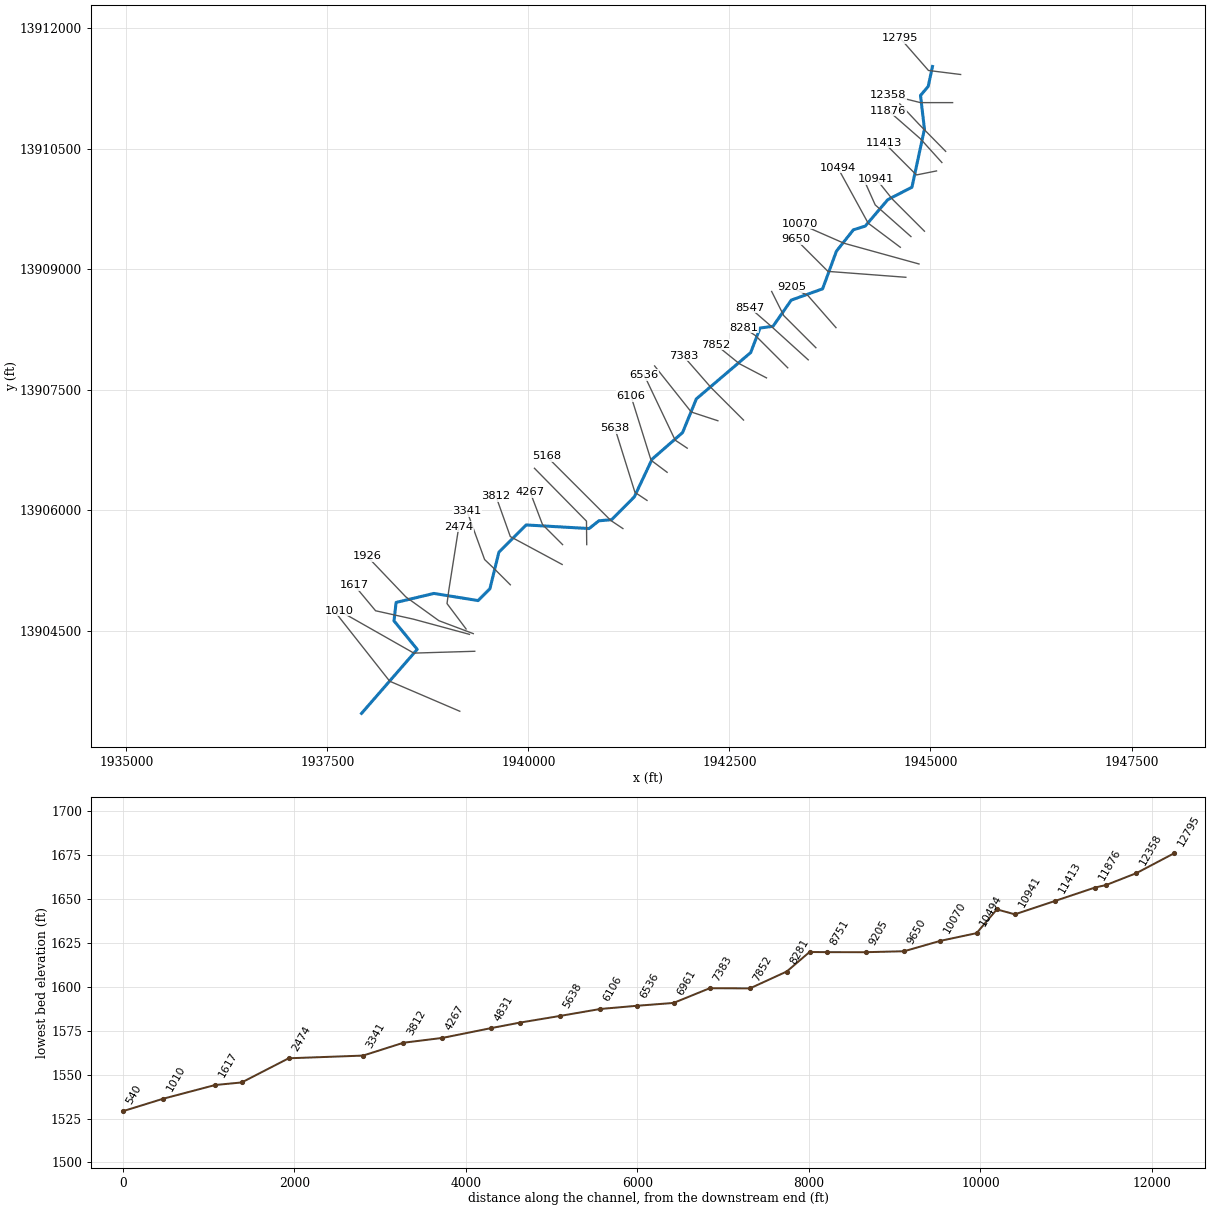
--- Silver Creek.prj (project) ---

Proj Title=Silver Creek Base Level Engineering
Current Plan=p01
Default Exp/Contr=0.3,0.1
English Units
Geom File=g01
Flow File=f01
Plan File=p01
Y Axis Title=Elevation
X Axis Title(PF)=Main Channel Distance
X Axis Title(XS)=Station
BEGIN DESCRIPTION:
Silver Creek
END DESCRIPTION:
DSS Export Rating Curves= 0
DSS Export Rating Curve Sorted= 0
DSS Export Volume Flow Curves= 0
DXF OffsetX= 0
DXF OffsetY= 0
DXF ScaleX= 1
DXF ScaleY= 10

--- Silver Creek.p01 (plan) ---

Plan Title=Multiple Run
Short Identifier=Multiple
Geom File=g01
Flow File=f01
Subcritical Flow
K Sum by GR= 0
Std Step Tol= 0.01
Critical Tol= 0.01
Num of Std Step Trials= 20
Max Error Tol= 0.3
Flow Tol Ratio= 0.001
Split Flow NTrial= 30
Split Flow Tol= 0.02
Split Flow Ratio= 0.02
Log Output Level= 0
Friction Slope Method= 1
Unsteady Friction Slope Method= 2
Unsteady Bridges Friction Slope Method= 1
Parabolic Critical Depth
Global Vel Dist=  1 , 1 , 1
Global Log Level= 0
CheckData=True
Encroach Param= -1, 0, 0, 0
BEGIN DESCRIPTION:
Multiple Run
END DESCRIPTION:

--- Silver Creek.f01 (steady flow) ---

Flow Title=Multiple
Number of Profiles=7
Profile Names=10-year,25-year,50-year,1pct_min,100-year,1pct_plu,500-year
River Rch & RM= Silver Creek,Reach-1,12795
    1794    3152    4486    3086    6158   12286   11457
River Rch & RM= Silver Creek,Reach-1,10731
    3066    5516    7971    5554   11082   22112   21173
River Rch & RM= Silver Creek,Reach-1,5168
    3945    7172   10438    7317   14599   29129   28237
River Rch & RM= Silver Creek,Reach-1,1926
    4615    8449   12352    8694   17347   34613   33831
Boundary for River Rch & Prof#=Silver Creek,Reach-1,1
Up Type=0
Dn Type=3
Dn Slope=0.005
Boundary for River Rch & Prof#=Silver Creek,Reach-1,2
Up Type=0
Dn Type=3
Dn Slope=0.005
Boundary for River Rch & Prof#=Silver Creek,Reach-1,3
Up Type=0
Dn Type=3
Dn Slope=0.005
Boundary for River Rch & Prof#=Silver Creek,Reach-1,4
Up Type=0
Dn Type=3
Dn Slope=0.005
Boundary for River Rch & Prof#=Silver Creek,Reach-1,5
Up Type=0
Dn Type=3
Dn Slope=0.005
Boundary for River Rch & Prof#=Silver Creek,Reach-1,6
Up Type=0
Dn Type=3
Dn Slope=0.005
Boundary for River Rch & Prof#=Silver Creek,Reach-1,7
Up Type=0
Dn Type=3
Dn Slope=0.005

--- Silver Creek.g01 (geometry) ---

Geom Title=Existing Conditions
Program Version=4.10

River Reach=Silver Creek    ,Reach-1
Reach XY= 30
        1945025.       13911525.      1944971.45     13911276.47
      1944876.04     13911164.56      1944924.93     13910745.03
      1944769.48     13910022.56       1944468.8     13909867.21
      1944188.33     13909538.39      1944041.46     13909492.13
      1943830.83      13909227.3      1943658.52     13908757.94
      1943268.48     13908617.32      1943041.76     13908291.43
      1942880.44     13908269.81      1942764.52      13907965.2
      1942088.39     13907388.33      1941916.82     13906968.96
      1941538.48     13906638.56      1941316.86     13906168.94
      1941034.84     13905885.39      1940876.47     13905871.44
      1940754.95     13905774.79      1939972.55     13905819.53
      1939632.88     13905481.16      1939521.39      13905026.5
      1939373.54     13904878.54        1938825.     13904967.44
      1938354.41     13904855.43      1938328.53     13904626.46
       1938617.4     13904271.66        1937925.       13903475.

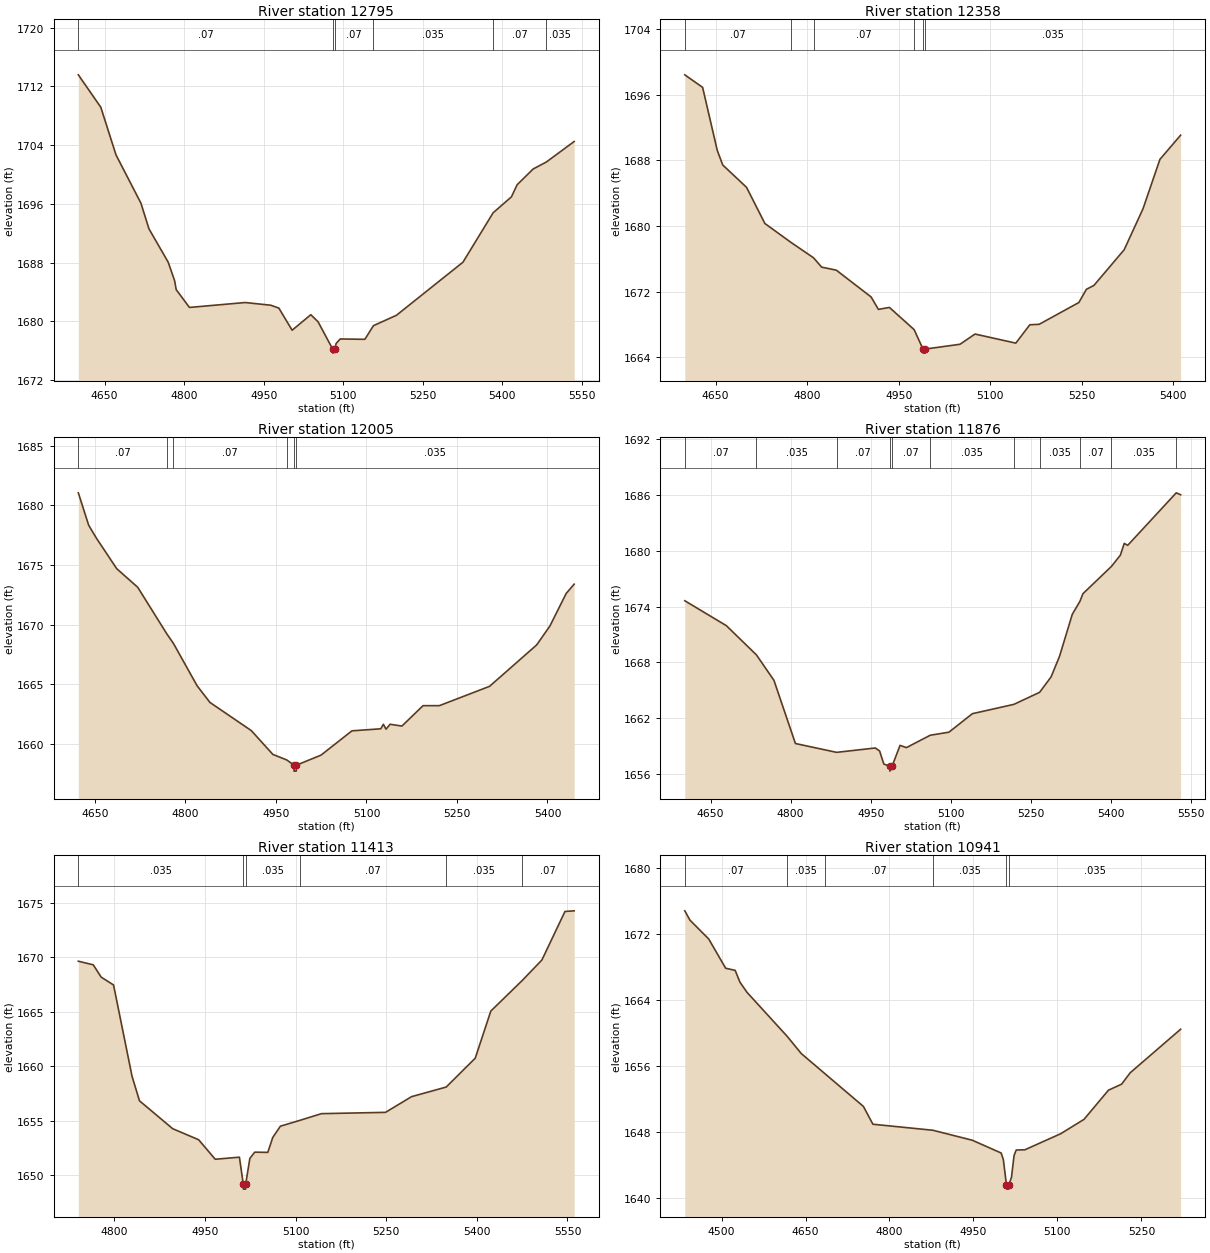
Type RM Length L Ch R = 1 ,12795   ,437,437,437
BEGIN DESCRIPTION:
Silver Creek 27.0
END DESCRIPTION:
XS GIS Cut Line= 3
      1945375.03       13911425.        1944975.       13911475.
      1944625.03     13911874.97
#Sta/Elev= 30
  4600.6 1713.58    4643 1709.16  4671.6 1702.68  4718.6 1696.11  4733.7 1692.62
    4770 1688.07  4782.1 1685.55  4785.1 1684.33  4810.1 1681.91  4915.1 1682.58
  4963.5 1682.21  4978.6 1681.82  5003.6 1678.81  5038.8 1680.92  5052.5 1679.96
  5080.4 1676.19  5080.6 1675.69  5084.4 1676.19  5086.4 1676.99  5094.3 1677.62
  5140.7 1677.57  5156.9 1679.43  5200.2 1680.84  5325.6 1688.07  5382.5  1694.8
  5416.9 1696.96  5427.7 1698.61  5457.9 1700.76  5482.8 1701.71  5535.2  1704.5
#Mann= 6 ,-1 , 0
  4600.6     .07       0  5080.4     .05       0  5084.4     .07       0
  5156.9    .035       0  5382.5     .07       0  5482.8    .035       0
Bank Sta=5080.4,5084.4
XS Rating Curve= 0 ,0
Exp/Cntr=0.3,0.1

Type RM Length L Ch R = 1 ,12358   ,353,353,353
BEGIN DESCRIPTION:
Silver Creek 26.0
END DESCRIPTION:
XS GIS Cut Line= 3
      1945275.04       13911075.        1944875.       13911075.
      1944475.05     13911174.99
#Sta/Elev= 30
  4599.5 1698.46  4628.7 1696.93  4652.7 1689.23  4661.7 1687.45  4700.7 1684.72
  4730.7 1680.31  4772.9 1678.03  4810.4 1676.12  4823.7 1674.98  4847.7 1674.61
  4904.7 1671.34  4916.7 1669.82  4934.7 1670.06  4975.2 1667.35  4989.7 1664.98
    4990 1664.48  4993.5 1664.48  4993.7 1664.98  5050.3 1665.56    5075 1666.81
  5141.8  1665.7  5164.7 1667.94  5180.1    1668  5245.1 1670.66  5257.4 1672.27
  5269.8 1672.75  5319.3  1677.1  5350.2 1682.11  5377.9 1688.14  5411.8 1691.09
#Mann= 6 ,-1 , 0
  4599.5     .07       0  4772.9    .035       0  4810.4     .07       0
  4975.2    .035       0  4989.7    .035       0  4993.7    .035       0
Bank Sta=4989.7,4993.7
XS Rating Curve= 0 ,0
Exp/Cntr=0.3,0.1

Type RM Length L Ch R = 1 ,12005   ,129,129,129
BEGIN DESCRIPTION:
Silver Creek 25.1
END DESCRIPTION:
XS GIS Cut Line= 3
      1945188.79     13910468.73      1944857.77      13910805.2
      1944618.15     13911059.76
#Sta/Elev= 30
  4622.6 1681.05  4639.7 1678.34    4652 1677.29  4686.2 1674.69    4721 1673.13
  4769.4 1669.21  4780.2 1668.42  4819.4 1664.87  4840.7 1663.47  4909.2 1661.11
    4945 1659.11  4967.9 1658.65  4979.9 1658.21  4980.1 1657.71  4983.7 1657.71
    4984 1658.21  5024.7 1659.05    5076 1661.09  5123.7 1661.26  5128.1 1661.64
  5132.5 1661.23  5139.2 1661.64  5158.8 1661.49  5193.8  1663.2  5220.8  1663.2
    5304 1664.82    5382 1668.29  5403.9 1669.87    5431 1672.61  5444.2 1673.39
#Mann= 6 ,-1 , 0
  4622.6     .07       0  4769.4    .035       0  4780.2     .07       0
  4967.9    .035       0  4979.9    .035       0    4984    .035       0
Bank Sta=4979.9,4984
XS Rating Curve= 0 ,0
Exp/Cntr=0.3,0.1

Type RM Length L Ch R = 1 ,11876   ,463,463,463
BEGIN DESCRIPTION:
Silver Creek 25.0
END DESCRIPTION:
XS GIS Cut Line= 3
      1945141.84     13910329.74        1944875.       13910625.
      1944474.98     13910975.02
#Sta/Elev= 30
  4601.5 1674.63  4679.4 1671.95  4735.9  1668.8  4768.6 1666.07  4808.9 1659.27
  4886.1 1658.32  4958.6 1658.79  4966.7 1658.47  4974.6 1657.07  4985.7  1656.8
    4986  1656.3  4989.9  1656.8    5005 1659.07    5017 1658.83  5061.6 1660.16
  5096.7 1660.49  5140.6 1662.48  5218.3 1663.48  5266.7 1664.78  5288.1 1666.43
    5304 1668.65  5327.9 1673.17  5342.2 1674.56  5347.9 1675.39  5401.4 1678.33
  5418.1 1679.54  5425.3  1680.8  5431.8 1680.59  5522.8 1686.24    5531 1686.03
#Mann= 11 ,-1 , 0
  4601.5     .07       0  4735.9    .035       0  4886.1     .07       0
  4985.7     .05       0  4989.9     .07       0  5061.6    .035       0
  5218.3     .07       0  5266.7    .035       0  5342.2     .07       0
  5401.4    .035       0  5522.8     .07       0
Bank Sta=4985.7,4989.9
XS Rating Curve= 0 ,0
Exp/Cntr=0.3,0.1

Type RM Length L Ch R = 1 ,11413   ,472,472,472
BEGIN DESCRIPTION:
Silver Creek 24.0
END DESCRIPTION:
XS GIS Cut Line= 3
      1945075.01       13910225.        1944825.       13910175.
      1944425.03     13910574.97
#Sta/Elev= 30
  4740.5 1669.62  4765.2 1669.29  4778.3 1668.16  4798.8 1667.44  4829.4 1659.07
  4841.7 1656.82  4896.7 1654.26  4939.6 1653.25  4967.1 1651.46  5007.1 1651.65
  5013.4 1649.22  5013.7 1648.72  5017.3 1648.72  5017.6 1649.22  5024.4 1651.54
  5032.5 1652.11  5054.1 1652.09  5062.2 1653.45  5074.9 1654.49  5106.8 1655.02
  5142.8 1655.64  5248.9 1655.76    5292  1657.2  5349.3 1658.08  5397.4 1660.73
  5423.2 1665.05  5475.1 1667.85  5507.7 1669.73  5545.9 1674.18  5561.1 1674.24
#Mann= 6 ,-1 , 0
  4740.5    .035       0  5013.4    .035       0  5017.6    .035       0
  5106.8     .07       0  5349.3    .035       0  5475.1     .07       0
Bank Sta=5013.4,5017.6
XS Rating Curve= 0 ,0
Exp/Cntr=0.3,0.1

Type RM Length L Ch R = 1 ,10941   ,210,210,210
BEGIN DESCRIPTION:
Silver Creek 23.0
END DESCRIPTION:
XS GIS Cut Line= 3
      1944924.97     13909475.03        1944525.       13909875.
        1944325.       13910125.
#Sta/Elev= 30
  4434.3 1674.81  4443.4 1673.69    4477  1671.4  4507.3 1667.85  4524.3 1667.59
  4532.8 1666.16  4545.5 1664.92  4617.1  1659.6  4642.4  1657.5  4684.8 1655.05
  4753.4 1651.09  4770.4 1648.93  4877.5  1648.2  4947.9 1646.99  4999.5 1645.44
  5003.4 1644.64    5009 1641.56  5009.2 1641.06  5012.9 1641.06  5013.2 1641.56
  5017.9 1642.49  5022.6 1645.15  5026.4  1645.8  5041.8 1645.83  5105.9 1647.78
  5147.5 1649.52  5191.2 1653.06  5214.7 1653.79    5230 1655.17  5320.1 1660.45
#Mann= 6 ,-1 , 0
  4434.3     .07       0  4617.1    .035       0  4684.8     .07       0
  4877.5    .035       0    5009    .035       0  5013.2    .035       0
Bank Sta=5009,5013.2
XS Rating Curve= 0 ,0
Exp/Cntr=0.3,0.1

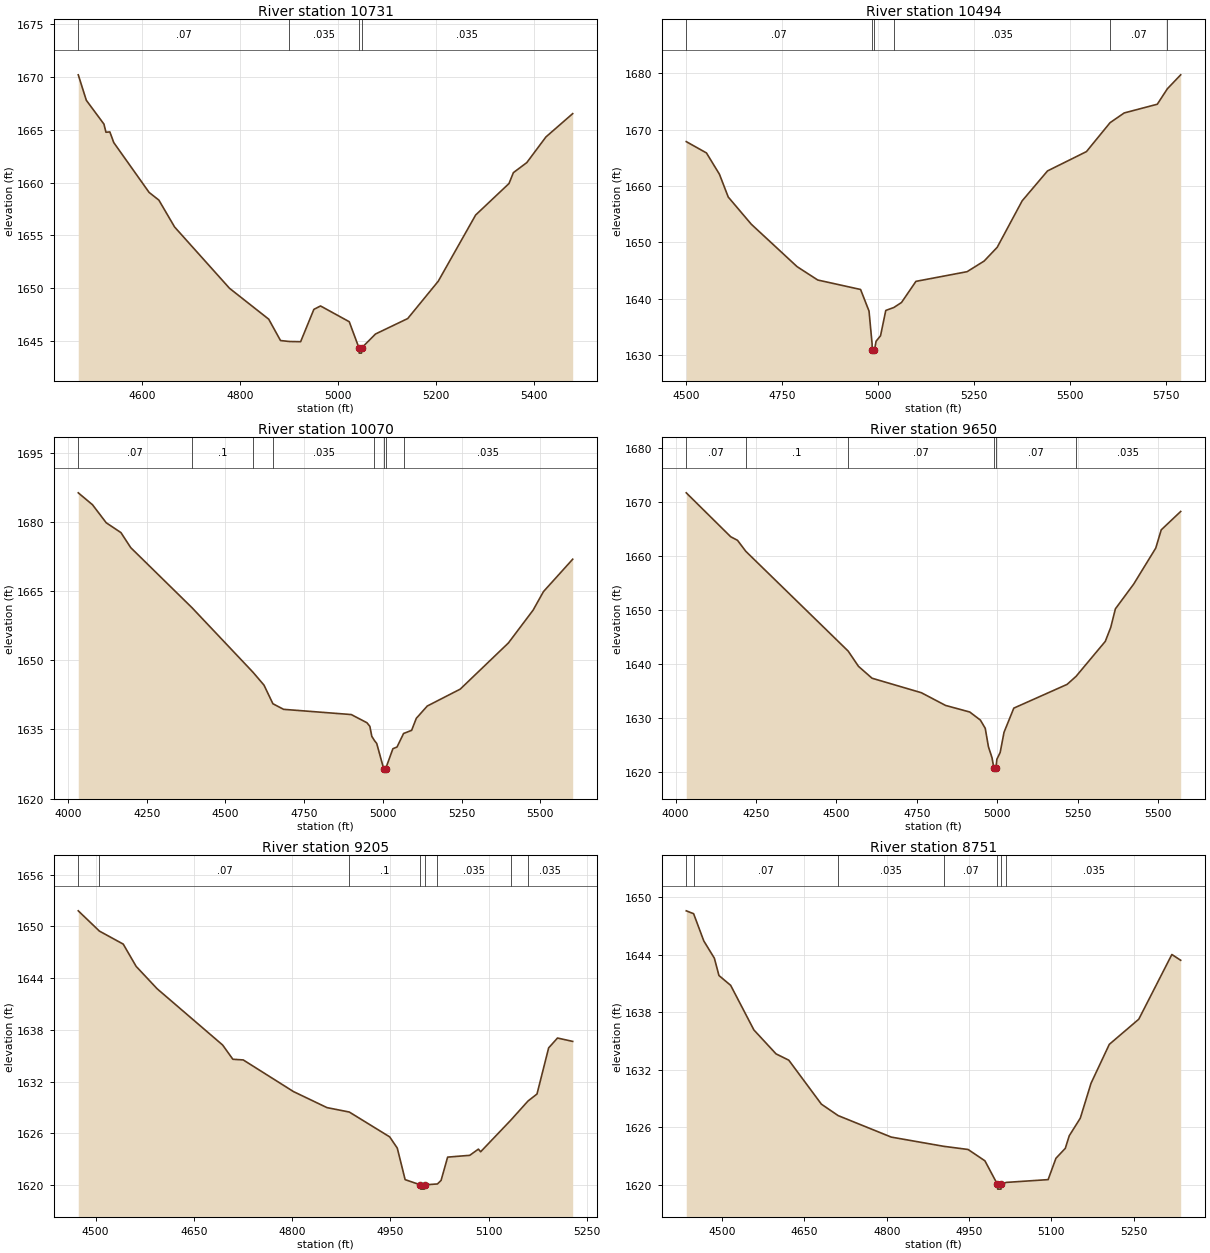
Type RM Length L Ch R = 1 ,10731   ,237,237,237
BEGIN DESCRIPTION:
Silver Creek 22.1
END DESCRIPTION:
XS GIS Cut Line= 3
      1944757.12     13909408.16      1944312.65     13909802.28
       1944142.5     13910182.51
#Sta/Elev= 30
  4469.4 1670.19  4485.9 1667.78  4521.9 1665.53    4526 1664.76    4534 1664.79
    4542 1663.78  4614.2 1659.07  4634.2 1658.34  4666.3  1655.8  4778.6    1650
  4858.7 1647.08  4882.8 1645.06  4901.1 1644.97  4923.9 1644.95    4951 1648.01
  4964.6 1648.33  5023.3 1646.84  5043.1 1644.37  5043.6 1643.87  5048.3 1643.87
  5048.8 1644.37    5077 1645.68  5142.8 1647.14  5205.2 1650.67  5281.6 1656.93
  5349.8 1659.91  5358.8 1660.94  5386.2 1661.89  5425.4 1664.32    5480 1666.52
#Mann= 4 ,-1 , 0
  4469.4     .07       0  4901.1    .035       0  5043.1    .035       0
  5048.8    .035       0
Bank Sta=5043.1,5048.8
XS Rating Curve= 0 ,0
Exp/Cntr=0.3,0.1

Type RM Length L Ch R = 1 ,10494   ,424,424,424
BEGIN DESCRIPTION:
Silver Creek 22.0
END DESCRIPTION:
XS GIS Cut Line= 3
        1944625.       13909275.        1944225.       13909575.
      1943846.09     13910267.18
#Sta/Elev= 30
  4500.5  1667.9  4553.2 1665.89    4587 1662.11    4610 1658.06    4670 1653.24
  4789.5  1645.7  4843.3 1643.33    4955 1641.65    4977 1637.82    4985 1632.01
  4985.4 1630.85  4985.8 1630.35  4991.1 1630.85  4995.4 1632.46    5007 1633.43
  5020.7 1637.93  5041.7 1638.45  5061.7 1639.34  5099.3 1643.09  5232.7 1644.81
  5277.2  1646.7  5311.2 1649.14  5376.3 1657.39  5442.4  1662.7  5543.9 1666.13
  5605.4 1671.26  5642.3 1672.99  5728.6 1674.54  5754.8 1677.28  5789.6 1679.76
#Mann= 6 ,-1 , 0
  4500.5     .07       0  4985.4     .05       0  4991.1     .07       0
  5041.7    .035       0  5605.4     .07       0  5754.8    .035       0
Bank Sta=4985.4,4991.1
XS Rating Curve= 0 ,0
Exp/Cntr=0.3,0.1

Type RM Length L Ch R = 1 ,10070   ,420,420,420
BEGIN DESCRIPTION:
Silver Creek 21.0
END DESCRIPTION:
XS GIS Cut Line= 3
      1944857.49     13909067.06        1943925.       13909325.
       1943372.7     13909567.01
#Sta/Elev= 30
  4032.5 1686.32  4077.8 1683.73  4121.4 1679.82  4168.1 1677.69  4199.2 1674.43
  4393.7 1661.41  4587.5 1647.41  4622.5 1644.61  4650.8 1640.57  4684.8 1639.36
  4899.6 1638.23  4949.4 1636.46  4958.7 1635.68  4964.9 1633.51  4973.2  1632.6
  4980.5 1631.96  5002.7 1626.46  5003.2 1625.96  5008.7 1626.46  5031.9 1630.82
    5045 1631.19  5065.8 1634.12  5091.4 1634.81  5106.3 1637.42  5141.1 1640.08
  5245.9 1643.75  5398.7 1653.75  5477.3 1660.88  5510.1 1664.89    5603 1671.92
#Mann= 8 ,-1 , 0
  4032.5     .07       0  4393.7      .1       0  4587.5     .07       0
  4650.8    .035       0  4973.2     .07       0  5002.7     .05       0
  5008.7     .07       0  5065.8    .035       0
Bank Sta=5002.7,5008.7
XS Rating Curve= 0 ,0
Exp/Cntr=0.3,0.1

Type RM Length L Ch R = 1 ,9650    ,445,445,445
BEGIN DESCRIPTION:
Silver Creek 20.0
END DESCRIPTION:
XS GIS Cut Line= 3
      1944693.61     13908901.55        1943725.       13908975.
      1943324.99     13909375.01
#Sta/Elev= 30
  4033.1 1671.72  4171.3 1663.57  4192.4 1662.91  4218.2 1660.87  4536.5 1642.35
  4568.4 1639.53  4610.6 1637.32  4763.9 1634.63  4839.2 1632.27  4914.4 1631.05
  4947.5 1629.55  4962.6 1628.02  4972.5  1624.6  4983.6 1622.58  4989.6 1620.58
  4990.1 1620.08  4995.7 1620.58  4998.7 1622.28    5009 1623.54    5021 1627.29
  5051.4 1631.77  5216.9 1636.17  5244.7 1637.65  5335.7 1644.15  5352.7 1646.74
  5367.2 1650.19  5424.1 1654.79  5492.7 1661.47  5509.7 1664.85  5570.2 1668.26
#Mann= 6 ,-1 , 0
  4033.1     .07       0  4218.2      .1       0  4536.5     .07       0
  4989.6     .05       0  4995.7     .07       0  5244.7    .035       0
Bank Sta=4989.6,4995.7
XS Rating Curve= 0 ,0
Exp/Cntr=0.3,0.1

Type RM Length L Ch R = 1 ,9205    ,454,454,454
BEGIN DESCRIPTION:
Silver Creek 19.0
END DESCRIPTION:
XS GIS Cut Line= 3
      1943824.99     13908275.01        1943475.       13908675.
        1943275.       13908775.
#Sta/Elev= 30
  4473.4 1651.81  4505.7 1649.46  4542.1 1647.95  4561.8 1645.37  4593.9 1642.77
  4693.9 1636.25  4709.5  1634.6  4725.4 1634.52  4802.1 1630.85  4853.3 1628.99
  4887.3 1628.48    4949  1625.6  4960.6  1624.3  4972.6 1620.64  4995.7 1620.04
  4996.2 1619.54  5002.1 1619.54  5002.6 1620.04  5021.9 1620.14  5027.5 1620.55
  5037.5 1623.25  5071.3 1623.46  5084.5 1624.18  5087.9 1623.87  5133.9 1627.53
  5160.3 1629.76    5174 1630.57  5191.8 1635.92  5205.3 1637.06  5228.5 1636.67
#Mann= 8 ,-1 , 0
  4473.4      .1       0  4505.7     .07       0  4887.3      .1       0
  4995.7     .05       0  5002.6      .1       0  5021.9    .035       0
  5133.9     .07       0  5160.3    .035       0
Bank Sta=4995.7,5002.6
XS Rating Curve= 0 ,0
Exp/Cntr=0.3,0.1

Type RM Length L Ch R = 1 ,8751    ,204,204,204
BEGIN DESCRIPTION:
Silver Creek 18.0
END DESCRIPTION:
XS GIS Cut Line= 3
      1943574.97     13908025.03        1943175.       13908425.
      1943024.98     13908725.04
#Sta/Elev= 30
  4434.6 1648.55    4448 1648.25  4466.6 1645.41  4485.8 1643.62  4494.2 1641.81
  4515.5 1640.79  4557.9 1636.14  4598.2 1633.65  4621.5 1632.99  4680.9 1628.41
  4711.4 1627.22  4808.2 1624.98  4903.8 1624.02  4948.2 1623.69  4978.9 1622.51
  5001.7 1620.06  5002.2 1619.56  5008.2 1619.56  5008.7 1620.06  5017.8 1620.26
  5094.1 1620.55  5108.3 1622.77  5125.4 1623.81  5132.6 1625.12  5152.7 1626.95
  5172.3 1630.59  5205.6 1634.64  5259.3 1637.26  5319.6    1644  5335.7  1643.4
#Mann= 7 ,-1 , 0
  4434.6      .1       0    4448     .07       0  4711.4    .035       0
  4903.8     .07       0  5001.7     .05       0  5008.7     .07       0
  5017.8    .035       0
Bank Sta=5001.7,5008.7
XS Rating Curve= 0 ,0
Exp/Cntr=0.3,0.1

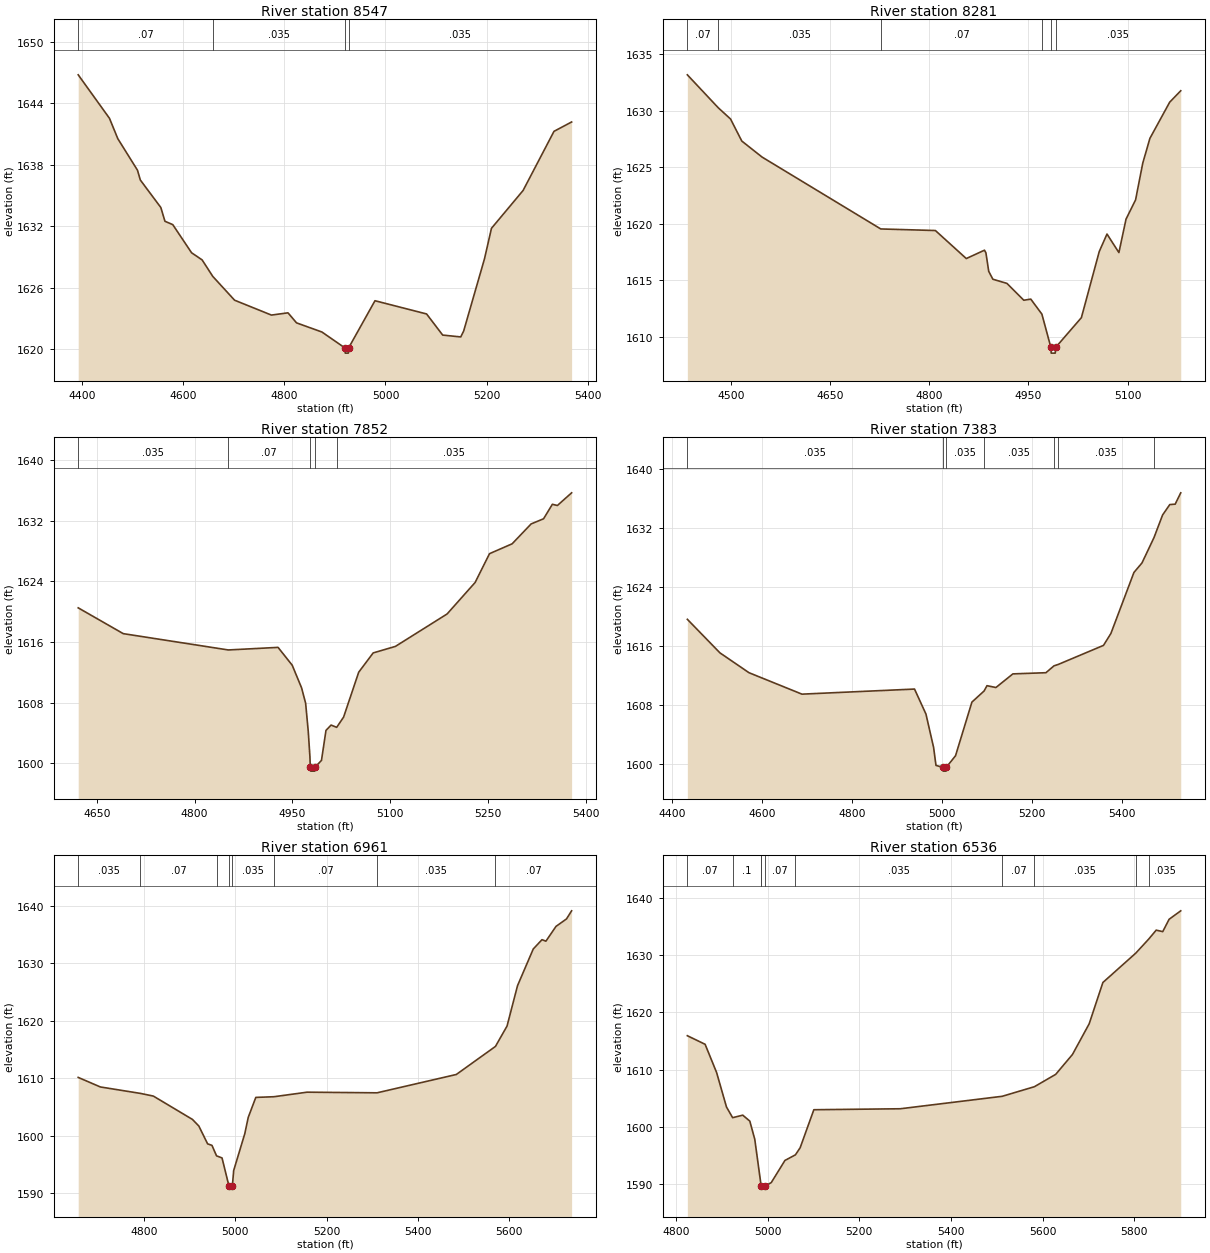
Type RM Length L Ch R = 1 ,8547    ,266,266,266
BEGIN DESCRIPTION:
Silver Creek 17.1
END DESCRIPTION:
XS GIS Cut Line= 3
      1943479.75     13907874.17       1943014.5     13908296.01
      1942752.34     13908523.46
#Sta/Elev= 30
  4392.8 1646.78  4454.6 1642.54    4471 1640.56  4509.9 1637.48  4515.6 1636.52
  4556.1 1633.84  4564.2  1632.5  4579.7 1632.17  4616.8 1629.43  4637.7 1628.73
  4658.8 1627.12  4701.9  1624.8  4774.7 1623.35  4807.4 1623.57  4824.3 1622.59
  4874.4  1621.7  4920.1 1620.14  4920.6 1619.64  4926.6 1619.64  4927.1 1620.14
  4979.3 1624.75  5081.3 1623.46  5113.1  1621.4  5148.8 1621.22  5154.6  1621.8
  5195.8 1628.85  5209.5 1631.81    5272  1635.5  5333.1 1641.27  5367.9 1642.18
#Mann= 4 ,-1 , 0
  4392.8     .07       0  4658.8    .035       0  4920.1    .035       0
  4927.1    .035       0
Bank Sta=4920.1,4927.1
XS Rating Curve= 0 ,0
Exp/Cntr=0.3,0.1

Type RM Length L Ch R = 1 ,8281    ,429,429,429
BEGIN DESCRIPTION:
Silver Creek 17.0
END DESCRIPTION:
XS GIS Cut Line= 3
      1943224.96     13907775.04        1942825.       13908175.
      1942675.01     13908274.99
#Sta/Elev= 30
  4434.3 1633.18  4481.1 1630.26  4499.6 1629.27  4516.6 1627.32  4547.3  1625.9
  4726.7 1619.54  4809.3  1619.4    4856 1616.92  4883.5 1617.66  4885.7 1617.42
  4889.9 1615.79  4896.2 1615.09  4917.5 1614.72  4942.9 1613.23  4953.5 1613.33
  4970.3    1612  4983.9 1609.05  4984.4 1608.55  4990.5 1608.55    4991 1609.05
    5030 1611.69    5057 1617.54  5068.7 1619.09  5086.7 1617.45  5097.5 1620.41
  5111.9 1622.11  5122.8 1625.37  5133.6 1627.56  5163.5 1630.76  5180.2 1631.77
#Mann= 6 ,-1 , 0
  4434.3     .07       0  4481.1    .035       0  4726.7     .07       0
  4970.3    .035       0  4983.9    .035       0    4991    .035       0
Bank Sta=4983.9,4991
XS Rating Curve= 0 ,0
Exp/Cntr=0.3,0.1

Type RM Length L Ch R = 1 ,7852    ,469,469,469
BEGIN DESCRIPTION:
Silver Creek 16.0
END DESCRIPTION:
XS GIS Cut Line= 3
      1942960.45     13907649.69        1942625.       13907825.
      1942330.86     13908062.73
#Sta/Elev= 30
  4621.5 1620.49  4690.6 1617.09  4851.7 1614.94    4928 1615.28  4949.7 1612.93
  4964.1 1609.94  4970.3 1607.91  4974.3 1604.21  4976.9 1600.83  4977.4 1599.47
  4977.9 1598.97  4984.1 1598.97  4984.6 1599.47  4994.6 1600.39  5001.5 1604.34
  5009.3 1605.04  5017.9 1604.74  5028.5 1606.09  5051.7 1612.01  5073.9 1614.55
    5108 1615.41  5187.2 1619.68  5230.2 1623.83  5252.3 1627.63    5287 1628.93
  5316.1 1631.55  5335.2 1632.23  5348.7 1634.14  5356.4 1633.98  5378.2 1635.65
#Mann= 5 ,-1 , 0
  4621.5    .035       0  4851.7     .07       0  4977.4     .05       0
  4984.6     .07       0  5017.9    .035       0
Bank Sta=4977.4,4984.6
XS Rating Curve= 0 ,0
Exp/Cntr=0.3,0.1

Type RM Length L Ch R = 1 ,7383    ,422,422,422
BEGIN DESCRIPTION:
Silver Creek 15.0
END DESCRIPTION:
XS GIS Cut Line= 3
      1942675.01     13907124.99        1942275.       13907525.
        1941925.     13907924.99
#Sta/Elev= 30
  4434.3 1619.66  4506.7 1615.11  4571.4 1612.41  4689.2  1609.5  4939.5 1610.19
  4964.9  1606.8  4981.9 1602.27  4987.2 1599.83  5002.7 1599.55  5003.2 1599.05
  5009.4 1599.05  5009.9 1599.55  5030.7 1601.14  5067.1 1608.42  5094.2 1609.93
  5100.6 1610.65  5120.5  1610.4  5158.2 1612.25  5231.7 1612.41  5249.6 1613.34
  5259.4 1613.54  5359.7 1616.12  5376.2 1617.74  5427.4 1626.02  5445.3 1627.31
    5472 1630.75  5491.2 1633.83  5507.2 1635.24  5519.1 1635.29  5531.5 1636.83
#Mann= 7 ,-1 , 0
  4434.3    .035       0  5002.7    .035       0  5009.9    .035       0
  5094.2    .035       0  5249.6     .07       0  5259.4    .035       0
    5472     .07       0
Bank Sta=5002.7,5009.9
XS Rating Curve= 0 ,0
Exp/Cntr=0.3,0.1

Type RM Length L Ch R = 1 ,6961    ,425,425,425
BEGIN DESCRIPTION:
Silver Creek 14.0
END DESCRIPTION:
XS GIS Cut Line= 3
       1942356.2     13907116.23        1942025.       13907225.
      1941569.44     13907798.47
#Sta/Elev= 30
  4655.6 1610.13  4704.1 1608.47  4791.8 1607.35  4820.3 1606.88  4905.9 1602.82
  4919.9 1601.67  4939.1 1598.57  4948.6 1598.31  4958.7 1596.48  4970.7 1596.12
    4986 1591.19  4986.5 1590.69  4993.3 1591.19  4996.2 1593.92  5020.6 1600.35
  5028.1 1603.17  5044.7 1606.65  5084.4 1606.77  5157.1 1607.56  5310.4 1607.45
    5484 1610.64  5569.7 1615.52  5595.1 1619.06  5618.1 1626.09  5652.6 1632.48
  5671.7  1634.1  5680.3 1633.84  5702.4 1636.41  5725.4 1637.71  5736.6 1639.12
#Mann= 8 ,-1 , 0
  4655.6    .035       0  4791.8     .07       0  4958.7    .035       0
    4986    .035       0  4993.3    .035       0  5084.4     .07       0
  5310.4    .035       0  5569.7     .07       0
Bank Sta=4986,4993.3
XS Rating Curve= 0 ,0
Exp/Cntr=0.3,0.1

Type RM Length L Ch R = 1 ,6536    ,430,430,430
BEGIN DESCRIPTION:
Silver Creek 13.0
END DESCRIPTION:
XS GIS Cut Line= 3
      1941974.96     13906775.02        1941825.       13906875.
      1941439.92     13907685.21
#Sta/Elev= 30
  4824.5 1615.92  4863.3 1614.42  4888.4 1609.48    4910 1603.44  4923.4 1601.58
  4945.5 1602.02  4960.9 1600.98  4971.7 1597.81  4984.4 1590.37  4985.6 1589.58
  4986.1 1589.08  4993.2 1589.58  5007.7 1590.22  5037.6  1594.1  5060.5 1595.08
  5070.8 1596.32  5100.7 1602.97  5289.4 1603.14    5512 1605.32  5582.3    1607
  5628.8 1609.16  5665.4 1612.64  5701.9 1618.01  5731.8 1625.23  5803.5 1630.36
  5831.8 1632.82  5848.2 1634.39  5862.5 1634.13  5876.4 1636.29  5901.8 1637.77
#Mann= 10 ,-1 , 0
  4824.5     .07       0  4923.4      .1       0  4984.4     .07       0
  4985.6     .05       0  4993.2     .07       0  5060.5    .035       0
    5512     .07       0  5582.3    .035       0  5803.5     .07       0
  5831.8    .035       0
Bank Sta=4985.6,4993.2
XS Rating Curve= 0 ,0
Exp/Cntr=0.3,0.1

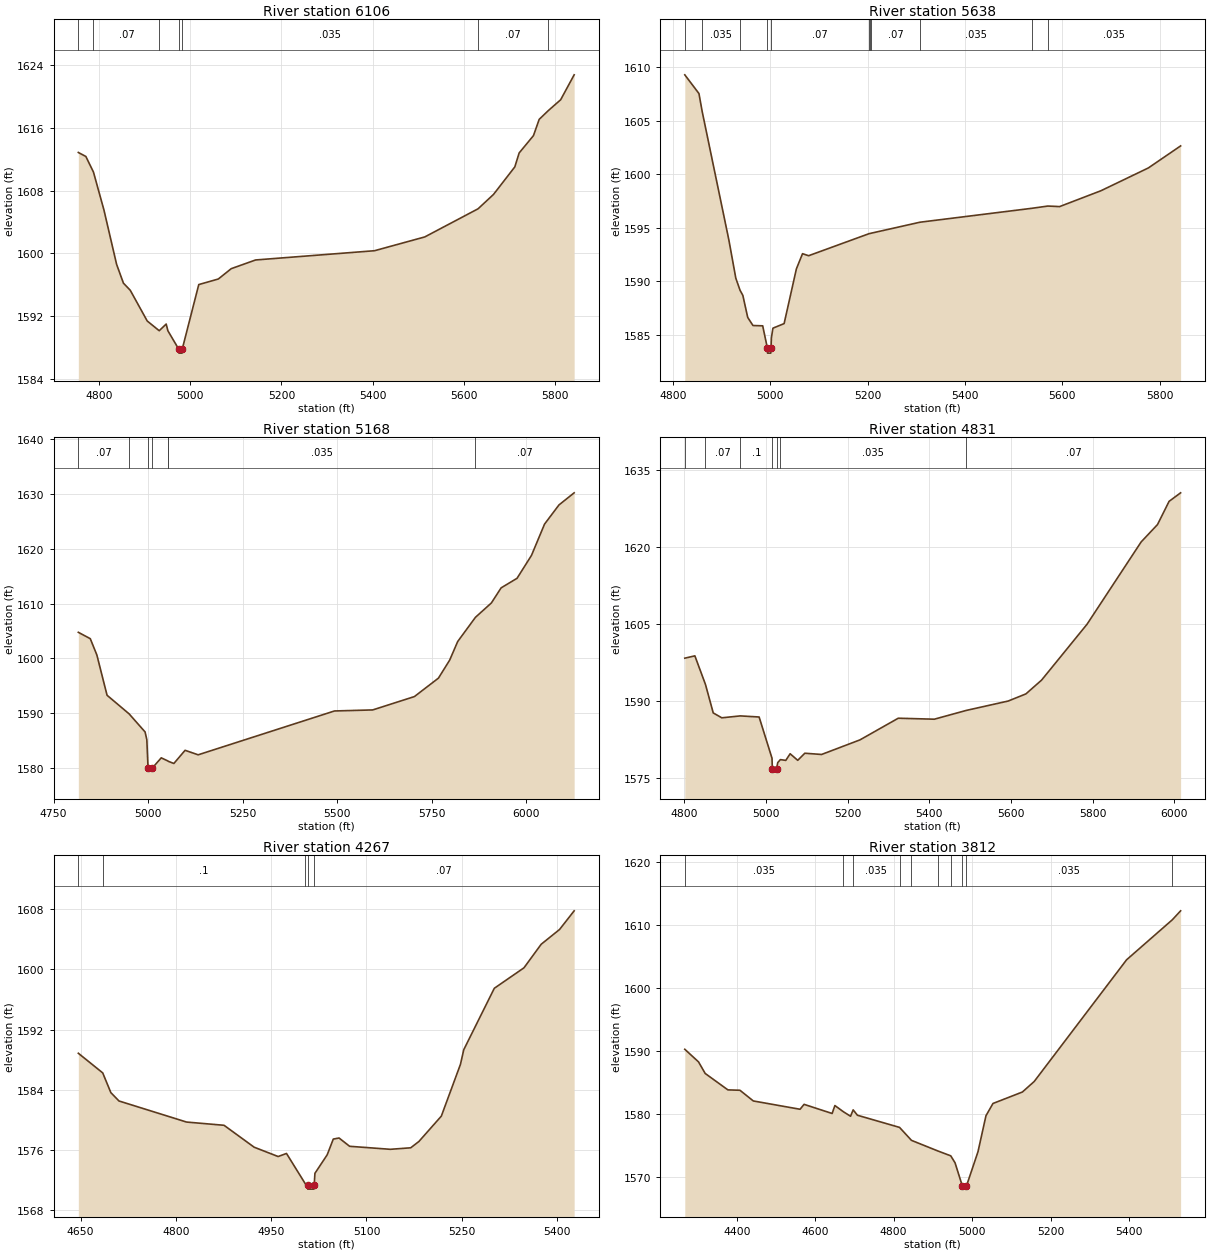
Type RM Length L Ch R = 1 ,6106    ,468,468,468
BEGIN DESCRIPTION:
Silver Creek 12.0
END DESCRIPTION:
XS GIS Cut Line= 3
      1941725.03     13906474.98        1941525.       13906625.
      1941275.03     13907424.91
#Sta/Elev= 30
  4754.3 1612.86  4770.8 1612.35  4787.5 1610.36  4810.5 1605.52  4838.3 1598.58
  4853.3 1596.18  4868.3 1595.27  4905.5 1591.35  4931.8 1590.11  4947.1 1590.96
  4950.8 1590.11  4974.7 1587.75  4975.2 1587.25  4981.8 1587.25  4982.3 1587.75
  5018.6    1596  5061.5 1596.71  5089.9 1598.03  5143.3 1599.14  5404.3 1600.32
  5514.6 1602.08  5631.5 1605.67  5665.5 1607.51  5712.2 1611.02  5721.7  1612.8
  5753.1 1615.01  5765.7 1617.09    5786 1618.22  5812.8 1619.59  5842.4 1622.77
#Mann= 7 ,-1 , 0
  4754.3      .1       0  4787.5     .07       0  4931.8    .035       0
  4974.7    .035       0  4982.3    .035       0  5631.5     .07       0
    5786    .035       0
Bank Sta=4974.7,4982.3
XS Rating Curve= 0 ,0
Exp/Cntr=0.3,0.1

Type RM Length L Ch R = 1 ,5638    ,470,470,470
BEGIN DESCRIPTION:
Silver Creek 11.0
END DESCRIPTION:
XS GIS Cut Line= 3
      1941475.01       13906125.        1941325.       13906225.
      1941075.01     13907024.96
#Sta/Elev= 30
  4824.4  1609.3  4853.5 1607.55  4860.3 1605.83  4914.8  1593.9  4929.2  1590.3
  4937.9 1589.17  4943.6  1588.7  4953.6 1586.64  4964.4 1585.88  4984.4 1585.85
  4993.9  1583.8  4994.4  1583.3    5001  1583.3  5001.5  1583.8  5002.3 1584.74
  5005.4 1585.63  5028.4 1586.06  5053.6 1591.17  5066.2 1592.59  5078.7  1592.4
  5203.5 1594.47  5205.4 1594.48  5206.8  1594.5  5307.4 1595.53  5537.2 1596.83
  5570.1 1597.04  5594.2 1596.99  5679.1 1598.47  5776.5  1600.6  5842.8 1602.66
#Mann= 11 ,-1 , 0
  4824.4     .07       0  4860.3    .035       0  4937.9     .07       0
  4993.9    .035       0  5001.5     .07       0  5203.5     .07       0
  5205.4    .035       0  5206.8     .07       0  5307.4    .035       0
  5537.2     .07       0  5570.1    .035       0
Bank Sta=4993.9,5001.5
XS Rating Curve= 0 ,0
Exp/Cntr=0.3,0.1

Type RM Length L Ch R = 1 ,5168    ,337,337,337
BEGIN DESCRIPTION:
Silver Creek 10.0
END DESCRIPTION:
XS GIS Cut Line= 3
      1941175.01       13905775.        1941025.       13905875.
      1940224.97     13906675.03
#Sta/Elev= 30
  4815.5 1604.76  4847.1  1603.6  4864.5 1600.64  4891.5  1593.3  4949.9 1589.91
  4992.1 1586.62  4996.7 1585.22    5000 1579.99  5000.5 1579.49  5010.4 1579.99
  5034.9 1581.91  5052.4 1581.34  5053.5 1581.28  5068.2 1580.88  5097.9 1583.28
  5132.5 1582.46  5493.1 1590.44  5594.3 1590.63  5704.6 1593.06  5768.2 1596.42
  5797.9  1599.7  5819.1 1603.08  5866.1 1607.49  5908.2  1610.1    5934 1612.85
  5976.1 1614.59  6014.3 1618.76  6048.9 1624.46  6087.1 1627.95  6127.2 1630.15
#Mann= 7 ,-1 , 0
  4815.5     .07       0  4949.9      .1       0    5000     .05       0
  5010.4      .1       0  5052.4     .07       0  5053.5    .035       0
  5866.1     .07       0
Bank Sta=5000,5010.4
XS Rating Curve= 0 ,0
Exp/Cntr=0.3,0.1

Type RM Length L Ch R = 1 ,4831    ,564,564,564
BEGIN DESCRIPTION:
Silver Creek 9.0
END DESCRIPTION:
XS GIS Cut Line= 3
        1940725.     13905574.99      1940722.11     13905866.92
      1940074.99     13906525.01
#Sta/Elev= 30
  4800.8 1598.32  4825.5 1598.77  4851.5  1593.2  4870.5 1587.67  4891.5 1586.72
  4936.6 1587.09  4982.9 1586.88  5014.5 1578.86  5015.3 1576.85  5015.8 1576.35
  5025.7 1576.85  5028.6 1578.01    5035 1578.59  5048.3 1578.44  5058.9 1579.73
  5077.5 1578.45  5094.9 1579.83    5136 1579.59  5230.1 1582.43  5323.8 1586.64
  5412.2 1586.45  5490.1 1588.15  5593.1 1589.98  5636.6 1591.37  5675.1 1594.06
  5786.3 1604.91    5919 1620.93  5959.1 1624.31  5987.4 1628.82  6015.7 1630.48
#Mann= 7 ,-1 , 0
  4800.8    .035       0  4851.5     .07       0  4936.6      .1       0
  5015.3     .05       0  5025.7      .1       0    5035    .035       0
  5490.1     .07       0
Bank Sta=5015.3,5025.7
XS Rating Curve= 0 ,0
Exp/Cntr=0.3,0.1

Type RM Length L Ch R = 1 ,4267    ,455,455,455
BEGIN DESCRIPTION:
Silver Creek 8.0
END DESCRIPTION:
XS GIS Cut Line= 3
      1940425.02     13905574.98        1940175.       13905825.
      1940023.39     13906224.19
#Sta/Elev= 30
  4646.4 1588.86  4684.8 1586.25  4697.6 1583.63  4710.4 1582.52  4816.8 1579.72
  4875.8 1579.29  4923.2 1576.38    4961 1575.14  4974.1 1575.55  5003.5 1571.55
  5007.2 1571.31  5007.7 1570.81  5017.2 1570.81  5017.7 1571.31  5018.9 1572.91
  5038.2 1575.37  5047.8 1577.46  5056.9  1577.6  5073.5  1576.5  5137.6  1576.1
  5169.7  1576.3  5182.6 1577.14  5217.9 1580.51    5248 1587.39  5253.2 1589.33
  5301.3 1597.49    5348 1600.21  5375.1 1603.34    5404  1605.3    5427 1607.78
#Mann= 5 ,-1 , 0
  4646.4    .035       0  4684.8      .1       0  5003.5     .07       0
  5007.2     .05       0  5017.7     .07       0
Bank Sta=5007.2,5017.7
XS Rating Curve= 0 ,0
Exp/Cntr=0.3,0.1

Type RM Length L Ch R = 1 ,3812    ,471,471,471
BEGIN DESCRIPTION:
Silver Creek 7.0
END DESCRIPTION:
XS GIS Cut Line= 3
      1940419.61     13905327.96        1939775.       13905675.
      1939596.44     13906176.47
#Sta/Elev= 30
  4267.4 1590.29  4302.4 1588.29  4319.4 1586.45  4377.3 1583.84    4408 1583.78
  4442.1 1582.08  4561.3 1580.76  4571.6 1581.54  4643.1 1580.09  4650.2 1581.35
  4671.5 1580.38  4690.1 1579.65  4696.7 1580.66  4707.7 1579.81    4815 1577.88
  4845.4 1575.82  4912.5 1574.14  4945.6 1573.36  4956.6 1572.25  4975.2 1568.57
  4975.7 1568.07  4985.7 1568.57  5015.1 1574.02  5035.4 1579.73  5053.3 1581.68
  5128.3  1583.5  5158.4 1585.17    5394 1604.51  5510.5 1610.86  5531.8 1612.29
#Mann= 10 ,-1 , 0
  4267.4    .035       0  4671.5      .1       0  4696.7    .035       0
    4815      .1       0  4845.4    .035       0  4912.5      .1       0
  4945.6    .035       0  4975.2    .035       0  4985.7    .035       0
  5510.5     .07       0
Bank Sta=4975.2,4985.7
XS Rating Curve= 0 ,0
Exp/Cntr=0.3,0.1

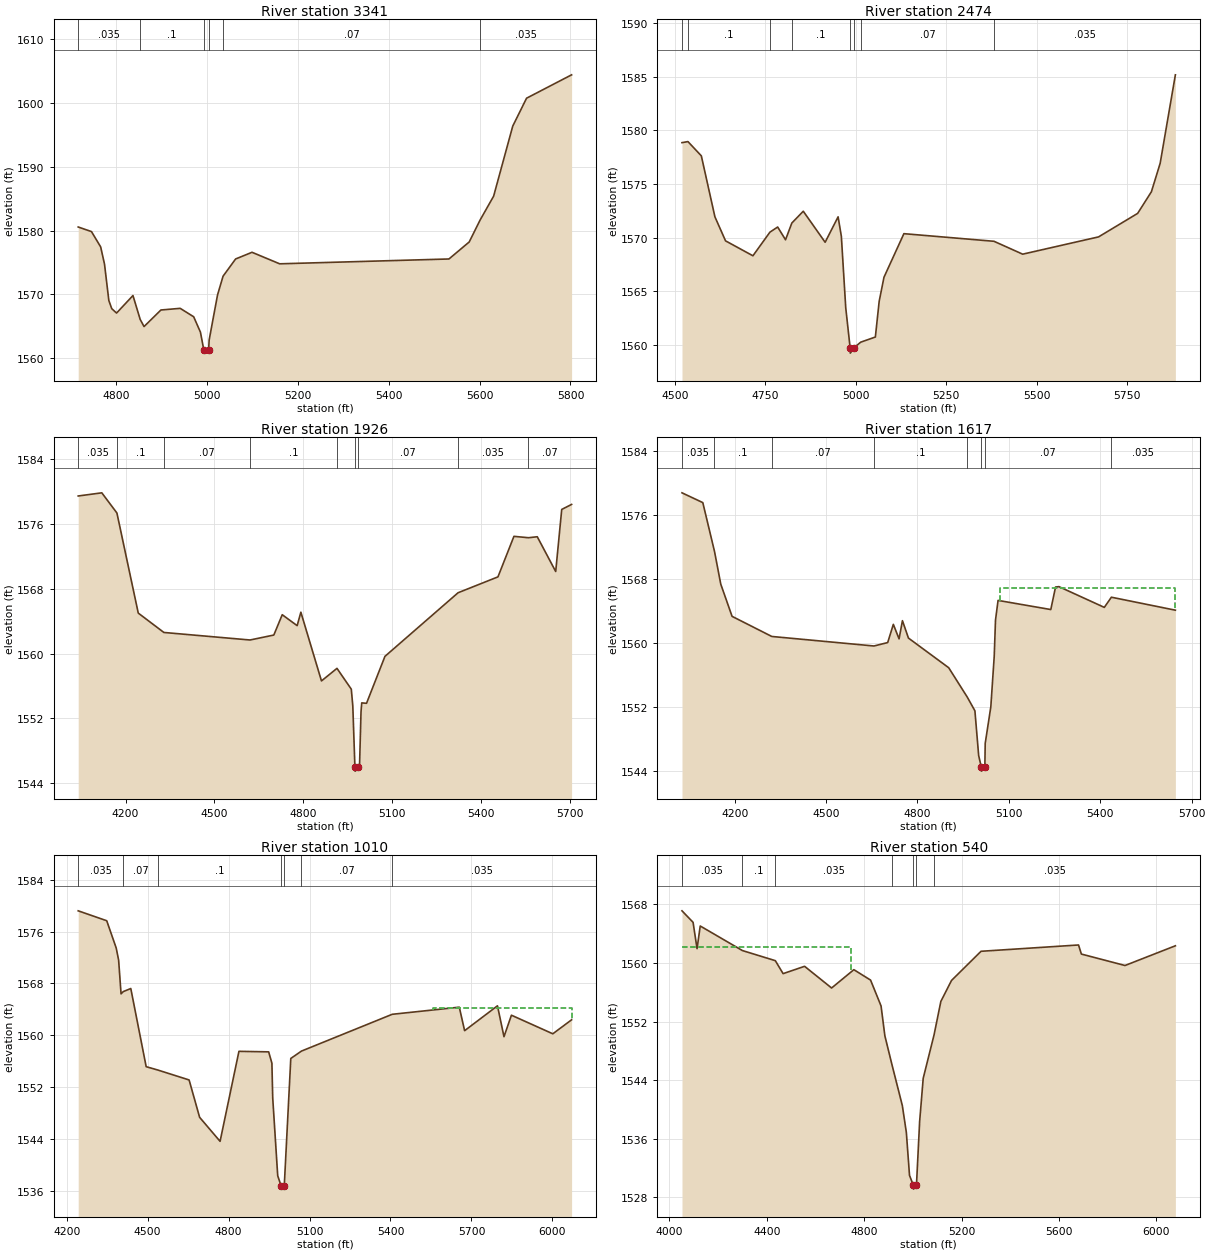
Type RM Length L Ch R = 1 ,3341    ,867,867,867
BEGIN DESCRIPTION:
Silver Creek 6.0
END DESCRIPTION:
XS GIS Cut Line= 4
        1939775.       13905075.        1939575.       13905275.
       1939455.3     13905389.19      1939237.58     13905988.39
#Sta/Elev= 30
  4716.7 1580.56  4745.9 1579.84  4766.1 1577.44  4774.6 1574.73  4784.1 1569.02
  4790.5 1567.74  4801.1 1567.05  4837.2  1569.8  4853.1 1566.05  4861.6 1564.93
  4898.7 1567.53  4941.1 1567.79  4970.8 1566.47  4985.7 1564.05  4993.1 1561.26
  4993.6 1560.76  5003.7 1561.26  5004.9 1562.83  5023.3 1569.89  5035.5 1572.84
  5063.1 1575.54  5099.2 1576.59  5160.1 1574.78  5532.6 1575.54  5577.2 1578.21
  5600.9 1581.62  5630.9  1585.4    5673  1596.4  5703.4 1600.78  5802.5 1604.45
#Mann= 6 ,-1 , 0
  4716.7    .035       0  4853.1      .1       0  4993.1     .05       0
  5003.7      .1       0  5035.5     .07       0  5600.9    .035       0
Bank Sta=4993.1,5003.7
XS Rating Curve= 0 ,0
Exp/Cntr=0.3,0.1

Type RM Length L Ch R = 1 ,2474    ,548,548,548
BEGIN DESCRIPTION:
Silver Creek 5.0
END DESCRIPTION:
XS GIS Cut Line= 4
        1939225.       13904525.      1938987.78     13904841.29
      1939008.56     13904998.11      1939134.49      13905797.2
#Sta/Elev= 30
    4520 1578.84  4536.4 1578.94  4573.4 1577.61  4610.9 1571.93  4640.3 1569.69
  4715.9  1568.3  4762.8  1570.5  4784.2 1570.98  4805.9 1569.79  4823.3 1571.35
  4854.9 1572.45  4915.3 1569.56  4951.1 1571.93  4960.1 1570.11  4972.2 1563.45
  4984.3 1559.73  4984.8 1559.23    4995 1559.73  5013.5 1560.25    5054 1560.73
  5064.5 1564.05  5077.8  1566.3  5132.8 1570.36  5381.6 1569.65  5460.8 1568.45
  5670.4 1570.06  5778.3 1572.25  5816.2 1574.26  5840.5 1576.92  5882.5 1585.16
#Mann= 8 ,-1 , 0
    4520    .035       0  4536.4      .1       0  4762.8     .07       0
  4823.3      .1       0  4984.3     .05       0    4995      .1       0
  5013.5     .07       0  5381.6    .035       0
Bank Sta=4984.3,4995
XS Rating Curve= 0 ,0
Exp/Cntr=0.3,0.1

Type RM Length L Ch R = 1 ,1926    ,309,309,309
BEGIN DESCRIPTION:
Silver Creek 4.0
END DESCRIPTION:
XS GIS Cut Line= 4
      1939314.33     13904467.36      1938886.49     13904628.52
        1938475.       13904925.      1937991.98     13905431.85
#Sta/Elev= 30
  4040.4 1579.44    4120 1579.83    4171 1577.34    4243 1564.99  4329.4  1562.6
  4619.9 1561.67  4700.3 1562.28  4728.7 1564.79    4779 1563.44  4791.6  1565.1
  4861.1 1556.62  4913.4 1558.17  4961.7  1555.6  4966.8 1553.53  4973.9 1545.99
  4974.4 1545.49  4985.5 1545.99  4989.4 1546.01  4994.5 1552.82  4996.9 1553.91
  5013.1 1553.86  5075.2 1559.65  5321.9  1567.5  5456.5 1569.46  5510.4 1574.46
  5559.3 1574.29  5589.1 1574.41  5651.3 1570.12  5671.6 1577.78  5704.9  1578.4
#Mann= 9 ,-1 , 0
  4040.4    .035       0    4171      .1       0  4329.4     .07       0
  4619.9      .1       0  4913.4     .07       0  4973.9     .05       0
  4985.5     .07       0  5321.9    .035       0  5559.3     .07       0
Bank Sta=4973.9,4985.5
XS Rating Curve= 0 ,0
Exp/Cntr=0.3,0.1

Type RM Length L Ch R = 1 ,1617    ,607,607,607
BEGIN DESCRIPTION:
Silver Creek 3.0
END DESCRIPTION:
XS GIS Cut Line= 4
       1939266.7     13904458.46      1938568.82     13904647.66
      1938099.29     13904751.88      1937833.34     13905071.33
#Sta/Elev= 30
  4026.9 1578.78  4095.2 1577.56  4133.6 1571.47  4154.2 1567.38  4191.3 1563.36
  4321.7 1560.85  4657.1 1559.66  4702.2 1560.09  4720.7 1562.36  4739.5 1560.55
  4750.6 1562.82  4770.3 1560.65  4902.4 1556.95  4963.1  1553.3  4988.5 1551.57
  5000.8 1545.99  5009.5 1544.54    5010 1544.04  5021.1 1544.54  5022.3  1547.5
  5040.7 1552.06  5051.9 1558.38  5056.1  1562.9  5064.5 1565.35  5237.6 1564.21
  5253.2 1567.02  5264.3 1567.07  5413.3 1564.48  5436.5 1565.75  5646.6 1564.13
#Mann= 8 ,-1 , 0
  4026.9    .035       0  4133.6      .1       0  4321.7     .07       0
  4657.1      .1       0  4963.1     .07       0  5009.5     .05       0
  5021.1     .07       0  5436.5    .035       0
#XS Ineff= 2 , 0
                         5069.51         1566.88
Permanent Ineff=
       F       F
Bank Sta=5009.5,5021.1
XS Rating Curve= 0 ,0
Exp/Cntr=0.3,0.1

Type RM Length L Ch R = 1 ,1010    ,470,470,470
BEGIN DESCRIPTION:
Silver Creek 2.0
END DESCRIPTION:
XS GIS Cut Line= 3
      1939332.57     13904247.77        1938575.       13904225.
      1937644.13     13904754.02
#Sta/Elev= 30
  4242.6 1579.21  4348.3 1577.68  4383.4 1573.47  4392.4  1571.6  4401.4 1566.39
  4409.9 1566.74  4437.5 1567.21  4494.5 1555.14  4537.2 1554.63  4653.6 1553.09
  4692.6 1547.32  4768.4 1543.61  4838.3 1557.51  4948.5 1557.43  4960.5 1555.67
  4963.5 1550.32    4982  1538.3  4994.7 1536.73  4995.2 1536.23  5006.3 1536.73
  5030.5 1556.41  5070.1 1557.55  5406.4 1563.23    5655 1564.33  5674.7  1560.7
  5796.5 1564.54  5820.6 1559.77  5848.2 1563.09  6001.6 1560.22  6071.2 1562.38
#Mann= 7 ,-1 , 0
  4242.6    .035       0  4409.9     .07       0  4537.2      .1       0
  4994.7     .05       0  5006.3      .1       0  5070.1     .07       0
  5406.4    .035       0
#XS Ineff= 2 , 0
                          5558.3         1564.25
Permanent Ineff=
       F       F
Bank Sta=4994.7,5006.3
XS Rating Curve= 0 ,0
Exp/Cntr=0.3,0.1

Type RM Length L Ch R = 1 ,540     ,0,0,0
BEGIN DESCRIPTION:
Silver Creek 1.0
END DESCRIPTION:
XS GIS Cut Line= 3
      1939146.61     13903501.34        1938275.       13903875.
      1937608.04     13904721.37
#Sta/Elev= 30
  4051.7  1567.1  4097.2 1565.53  4113.5 1561.94  4126.6 1565.03  4299.7 1561.68
  4434.9  1560.3  4466.9 1558.53  4555.1 1559.53    4666 1556.57  4757.4 1559.07
    4826 1557.65  4869.1 1554.12  4884.7 1550.05  4913.2  1546.2  4956.5 1540.52
  4972.9 1536.87  4985.9 1531.01  5001.9 1529.63  5002.4 1529.13  5014.4 1529.63
  5027.5 1538.36  5042.1 1544.24  5086.7 1550.18  5114.6 1554.74  5158.4  1557.6
  5279.6 1561.58  5679.9 1562.44  5691.6  1561.2  5870.8 1559.64  6077.6 1562.33
#Mann= 7 ,-1 , 0
  4051.7    .035       0  4299.7      .1       0  4434.9    .035       0
  4913.2      .1       0  5001.9     .05       0  5014.4      .1       0
  5086.7    .035       0
#XS Ineff= 2 , 0
         4745.52 1562.13
Permanent Ineff=
       F       F
Bank Sta=5001.9,5014.4
XS Rating Curve= 0 ,0
Exp/Cntr=0.3,0.1

Chan Stop Cuts=-1
Use User Specified Reach Order=0
Composite Channel Slope=5