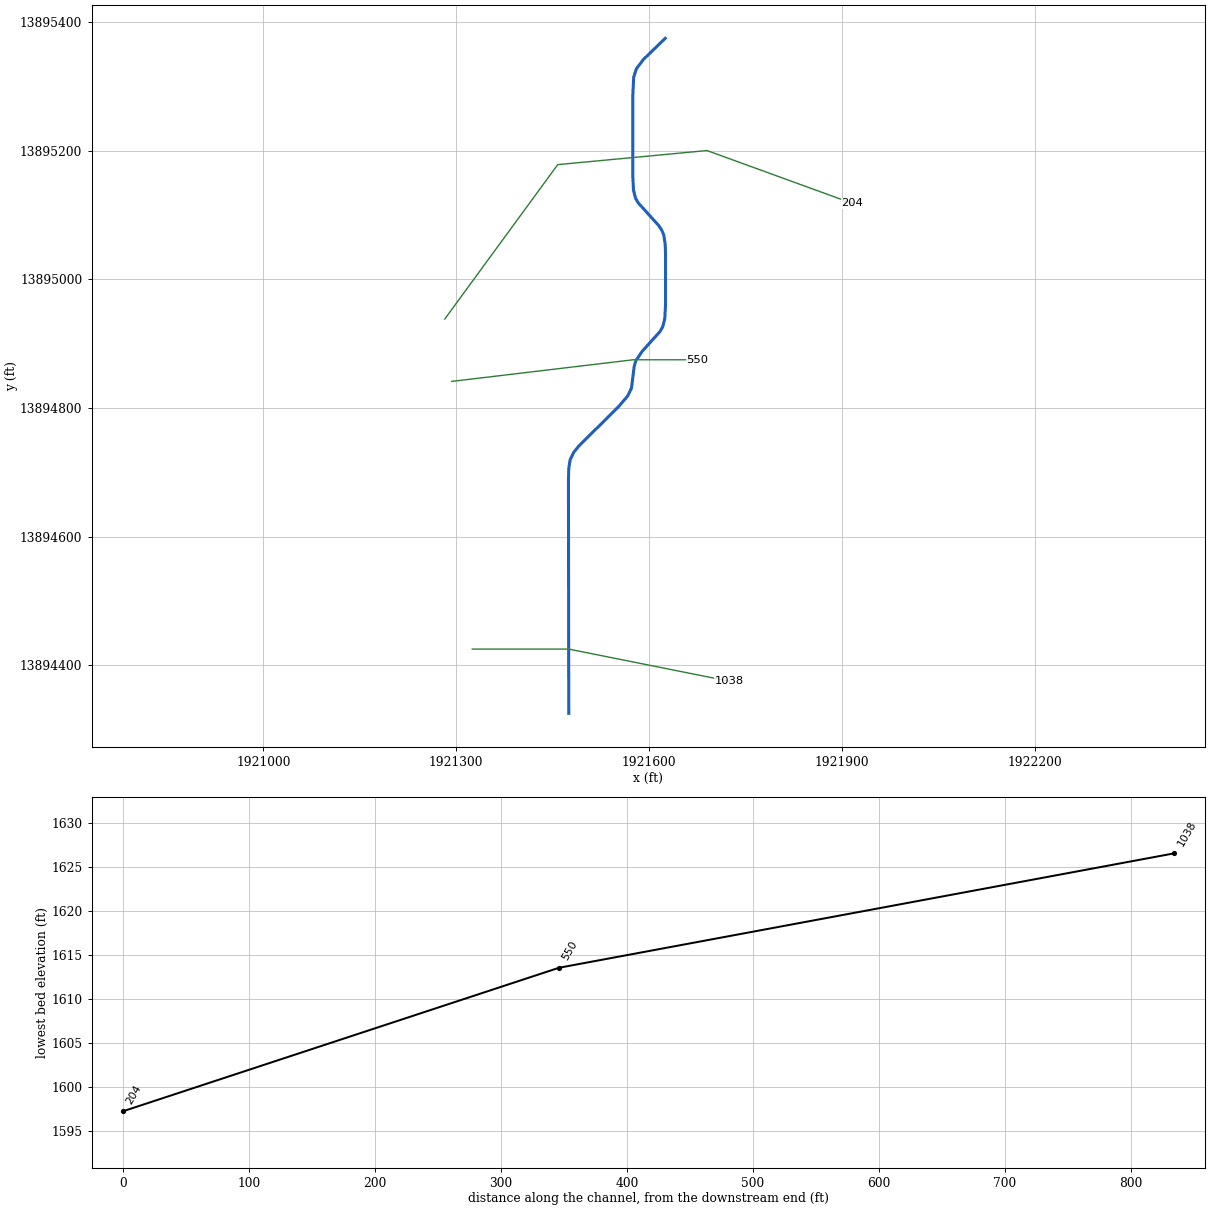
--- South Creek.prj (project) ---

Proj Title=South Creek Base Level Engineering
Current Plan=p01
Default Exp/Contr=0.3,0.1
English Units
Geom File=g01
Flow File=f01
Plan File=p01
Y Axis Title=Elevation
X Axis Title(PF)=Main Channel Distance
X Axis Title(XS)=Station
BEGIN DESCRIPTION:
South Creek
END DESCRIPTION:
DSS Export Rating Curves= 0
DSS Export Rating Curve Sorted= 0
DSS Export Volume Flow Curves= 0
DXF OffsetX= 0
DXF OffsetY= 0
DXF ScaleX= 1
DXF ScaleY= 10

--- South Creek.p01 (plan) ---

Plan Title=Multiple Run
Short Identifier=Multiple
Geom File=g01
Flow File=f01
Subcritical Flow
K Sum by GR= 0
Std Step Tol= 0.01
Critical Tol= 0.01
Num of Std Step Trials= 20
Max Error Tol= 0.3
Flow Tol Ratio= 0.001
Split Flow NTrial= 30
Split Flow Tol= 0.02
Split Flow Ratio= 0.02
Log Output Level= 0
Friction Slope Method= 1
Unsteady Friction Slope Method= 2
Unsteady Bridges Friction Slope Method= 1
Parabolic Critical Depth
Global Vel Dist=  1 , 1 , 1
Global Log Level= 0
CheckData=True
Encroach Param= -1, 0, 0, 0
BEGIN DESCRIPTION:
Multiple Run
END DESCRIPTION:

--- South Creek.f01 (steady flow) ---

Flow Title=Multiple
Program Version=4.10
Number of Profiles= 7
Profile Names=10-year,25-year,50-year,1pct_min,100-year,1pct_plu,500-year
River Rch & RM=South Creek,Reach-1         ,1038
    1139    1943    2712    1831    3654    7290    6546
Boundary for River Rch & Prof#=South Creek,Reach-1         , 1
Up Type= 0
Dn Type= 3
Dn Slope=0.01
Boundary for River Rch & Prof#=South Creek,Reach-1         , 2
Up Type= 0
Dn Type= 3
Dn Slope=0.01
Boundary for River Rch & Prof#=South Creek,Reach-1         , 3
Up Type= 0
Dn Type= 3
Dn Slope=0.01
Boundary for River Rch & Prof#=South Creek,Reach-1         , 4
Up Type= 0
Dn Type= 3
Dn Slope=0.01
Boundary for River Rch & Prof#=South Creek,Reach-1         , 5
Up Type= 0
Dn Type= 3
Dn Slope=0.01
Boundary for River Rch & Prof#=South Creek,Reach-1         , 6
Up Type= 0
Dn Type= 3
Dn Slope=0.01
Boundary for River Rch & Prof#=South Creek,Reach-1         , 7
Up Type= 0
Dn Type= 3
Dn Slope=0.01
DSS Import GetInterval= 0
DSS Import GetPeak= 0
DSS Import FillOption= 0

--- South Creek.g01 (geometry) ---

Geom Title=Existing Conditions
Program Version=4.10

River Reach=South Creek     ,Reach-1
Reach XY= 30
        1921475.       13894325.       1921474.5     13894688.84
      1921475.09     13894706.78      1921477.18     13894719.55
      1921482.83     13894731.19      1921491.46     13894741.75
      1921551.94     13894801.55      1921566.84     13894818.95
       1921572.5     13894831.04      1921576.72     13894864.29
      1921579.22     13894873.25      1921589.05     13894888.03
      1921616.91     13894918.93      1921621.26     13894926.56
      1921624.35     13894938.92      1921625.49      13894961.2
      1921625.47     13895040.16      1921624.95     13895054.96
      1921622.75     13895069.06      1921619.26     13895077.33
      1921614.15     13895084.64      1921583.14     13895118.94
      1921578.78     13895126.57      1921575.68     13895138.92
      1921574.56     13895161.18      1921574.58     13895285.17
      1921575.96      13895314.6      1921580.14     13895327.59
      1921591.08     13895342.06        1921625.       13895375.

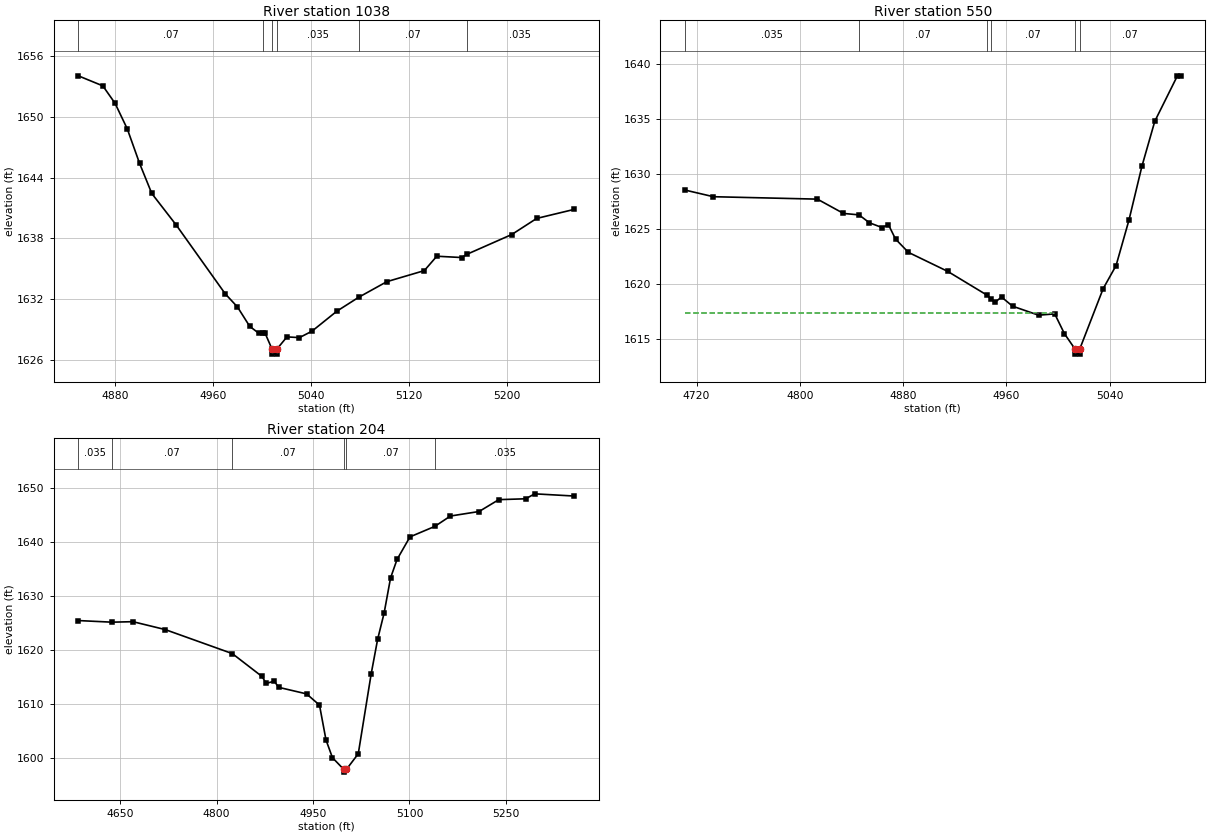
Type RM Length L Ch R = 1 ,1038    ,488,488,488
BEGIN DESCRIPTION:
South Creek 2.0
END DESCRIPTION:
XS GIS Cut Line= 3
      1921324.99       13894425.        1921475.       13894425.
      1921725.04     13894374.99
#Sta/Elev= 30
    4850 1654.05    4870 1653.06    4880 1651.34    4890 1648.81    4900 1645.42
    4910 1642.44    4930 1639.32    4970 1632.54    4980 1631.24    4990 1629.33
  4997.5 1628.64  5000.8 1628.64  5002.6 1628.64  5008.2 1627.09  5008.5 1626.59
    5012 1626.59  5012.2 1627.09  5020.4 1628.29  5030.6 1628.22  5040.8 1628.85
  5061.2 1630.83    5079  1632.2    5102 1633.74  5132.6 1634.83  5142.8 1636.25
  5163.2 1636.12  5167.2 1636.43    5204 1638.39  5224.4 1639.98    5255 1640.87
#Mann= 6 ,-1 , 0
    4850     .07       0  5000.8    .035       0  5008.2     .05       0
  5012.2    .035       0    5079     .07       0  5167.2    .035       0
Bank Sta=5008.2,5012.2
XS Rating Curve= 0 ,0
Exp/Cntr=0.3,0.1

Type RM Length L Ch R = 1 ,550     ,346,346,346
BEGIN DESCRIPTION:
South Creek 1.0
END DESCRIPTION:
XS GIS Cut Line= 3
      1921292.97     13894841.38        1921575.       13894875.
      1921674.98       13894875.
#Sta/Elev= 30
  4710.9 1628.52  4733.1 1627.91  4813.6 1627.69  4833.8 1626.39  4845.8 1626.26
  4853.9 1625.54  4863.6 1625.11  4868.6 1625.37  4874.1 1624.06  4884.1 1622.85
  4914.4 1621.13  4944.7 1618.98  4948.2 1618.61  4951.1 1618.31  4956.2 1618.79
  4964.7 1617.96  4984.9 1617.14  4997.4 1617.26  5004.9 1615.46  5012.9  1614.1
  5013.2  1613.6  5016.7  1613.6  5016.9  1614.1  5034.9 1619.55  5044.9 1621.65
  5054.9 1625.79  5064.9 1630.67  5074.9 1634.77  5092.4  1638.9  5094.9  1638.9
#Mann= 6 ,-1 , 0
  4710.9    .035       0  4845.8     .07       0  4944.7    .035       0
  4948.2     .07       0  5012.9     .05       0  5016.9     .07       0
#XS Ineff= 2 , 0
         4997.01 1617.31
Permanent Ineff=
       F       F
Bank Sta=5012.9,5016.9
XS Rating Curve= 0 ,0
Exp/Cntr=0.3,0.1

Type RM Length L Ch R = 1 ,204     ,0,0,0
BEGIN DESCRIPTION:
South Creek 0.0
END DESCRIPTION:
XS GIS Cut Line= 4
      1921282.15     13894938.44       1921457.8     13895178.53
      1921690.01     13895200.48      1921915.81     13895118.36
#Sta/Elev= 30
  4585.1 1625.43  4637.2 1625.13    4670 1625.22  4720.1 1623.76  4824.5  1619.3
  4870.7 1615.05  4877.3 1613.77  4889.8 1614.18  4896.5 1613.04    4940 1611.82
  4960.1 1609.74  4970.2 1603.28  4980.2 1599.99  4997.9  1597.8  4998.1  1597.3
  5001.9  1597.8  5020.4 1600.71  5040.5 1615.56  5050.5 1621.95  5060.6 1626.83
  5070.6 1633.34  5080.7 1636.77  5100.8 1640.96  5139.5 1642.91  5163.7 1644.83
  5208.3 1645.67  5238.9 1647.87  5280.8 1648.03  5294.7 1648.95  5356.1 1648.54
#Mann= 6 ,-1 , 0
  4585.1    .035       0  4637.2     .07       0  4824.5     .07       0
  4997.9     .05       0  5001.9     .07       0  5139.5    .035       0
Bank Sta=4997.9,5001.9
XS Rating Curve= 0 ,0
Exp/Cntr=0.3,0.1

Chan Stop Cuts=-1
Use User Specified Reach Order=0
Composite Channel Slope=5