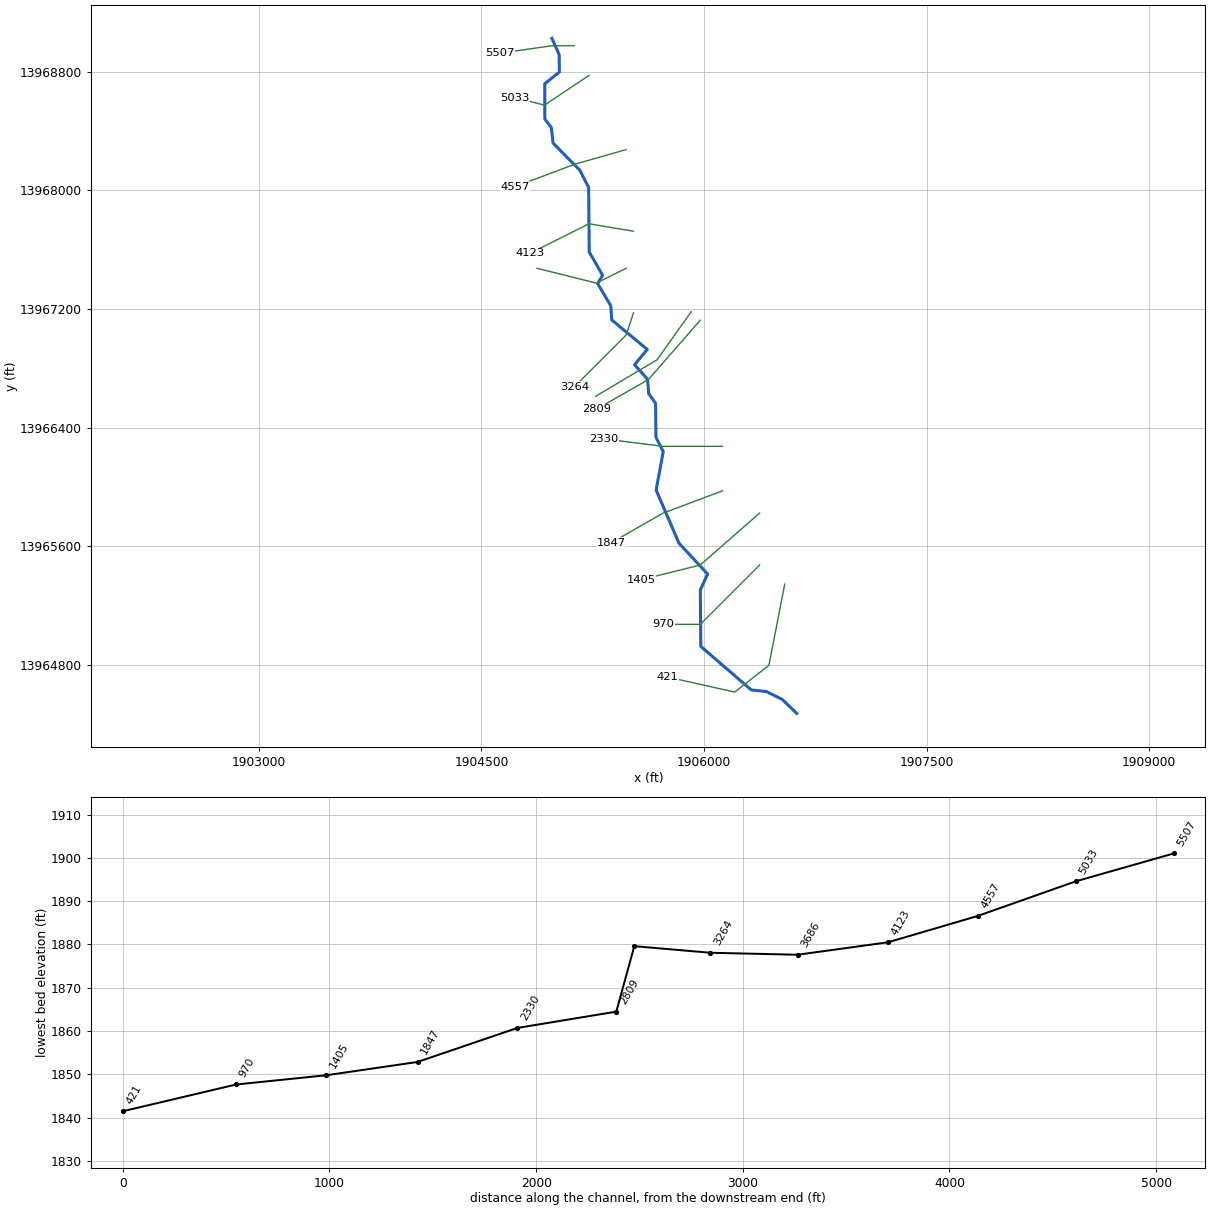
--- Spring Branch 2.prj (project) ---

Proj Title=Spring Branch 2 Base Level Engineering
Current Plan=p01
Default Exp/Contr=0.3,0.1
English Units
Geom File=g01
Flow File=f01
Plan File=p01
Y Axis Title=Elevation
X Axis Title(PF)=Main Channel Distance
X Axis Title(XS)=Station
BEGIN DESCRIPTION:
Spring Branch 2
END DESCRIPTION:
DSS Export Rating Curves= 0
DSS Export Rating Curve Sorted= 0
DSS Export Volume Flow Curves= 0
DXF OffsetX= 0
DXF OffsetY= 0
DXF ScaleX= 1
DXF ScaleY= 10

--- Spring Branch 2.p01 (plan) ---

Plan Title=Multiple Run
Short Identifier=Multiple
Geom File=g01
Flow File=f01
Subcritical Flow
K Sum by GR= 0
Std Step Tol= 0.01
Critical Tol= 0.01
Num of Std Step Trials= 20
Max Error Tol= 0.3
Flow Tol Ratio= 0.001
Split Flow NTrial= 30
Split Flow Tol= 0.02
Split Flow Ratio= 0.02
Log Output Level= 0
Friction Slope Method= 1
Unsteady Friction Slope Method= 2
Unsteady Bridges Friction Slope Method= 1
Parabolic Critical Depth
Global Vel Dist=  1 , 1 , 1
Global Log Level= 0
CheckData=True
Encroach Param= -1, 0, 0, 0
BEGIN DESCRIPTION:
Multiple Run
END DESCRIPTION:

--- Spring Branch 2.f01 (steady flow) ---

Flow Title=Multiple
Program Version=4.10
Number of Profiles= 7
Profile Names=10-year,25-year,50-year,1pct_min,100-year,1pct_plu,500-year
River Rch & RM=Spring Branch 2,Reach-1         ,5507
    2138    3790    5419    3737    7457   14879   13964
Boundary for River Rch & Prof#=Spring Branch 2,Reach-1         , 1
Up Type= 0
Dn Type= 3
Dn Slope=0.009
Boundary for River Rch & Prof#=Spring Branch 2,Reach-1         , 2
Up Type= 0
Dn Type= 3
Dn Slope=0.009
Boundary for River Rch & Prof#=Spring Branch 2,Reach-1         , 3
Up Type= 0
Dn Type= 3
Dn Slope=0.009
Boundary for River Rch & Prof#=Spring Branch 2,Reach-1         , 4
Up Type= 0
Dn Type= 3
Dn Slope=0.009
Boundary for River Rch & Prof#=Spring Branch 2,Reach-1         , 5
Up Type= 0
Dn Type= 3
Dn Slope=0.009
Boundary for River Rch & Prof#=Spring Branch 2,Reach-1         , 6
Up Type= 0
Dn Type= 3
Dn Slope=0.009
Boundary for River Rch & Prof#=Spring Branch 2,Reach-1         , 7
Up Type= 0
Dn Type= 3
Dn Slope=0.009
DSS Import GetInterval= 0
DSS Import GetPeak= 0
DSS Import FillOption= 0

--- Spring Branch 2.g01 (geometry) ---

Geom Title=Existing Conditions
Program Version=4.10

River Reach=Spring Branch 2 ,Reach-1
Reach XY= 30
        1904975.       13969025.      1905023.75     13968915.36
       1905025.2     13968797.69      1904927.01     13968719.32
      1904927.26     13968480.94      1904971.14      13968423.4
      1904982.86     13968318.83      1905164.24     13968134.68
      1905222.65     13968019.48      1905226.36     13967584.65
      1905316.76     13967428.23      1905283.24     13967371.77
      1905371.17     13967223.41      1905378.61     13967126.48
       1905617.4     13966928.35      1905532.11     13966825.01
      1905619.45     13966727.43      1905627.36     13966630.98
      1905673.78      13966564.5      1905676.22      13966335.5
      1905725.48      13966238.8      1905677.28     13965980.57
      1905830.83      13965622.7       1906024.4     13965414.38
      1905975.23     13965306.74      1905978.54     13964926.46
      1906318.83     13964632.86      1906419.03     13964622.67
      1906527.32     13964569.21        1906625.       13964475.

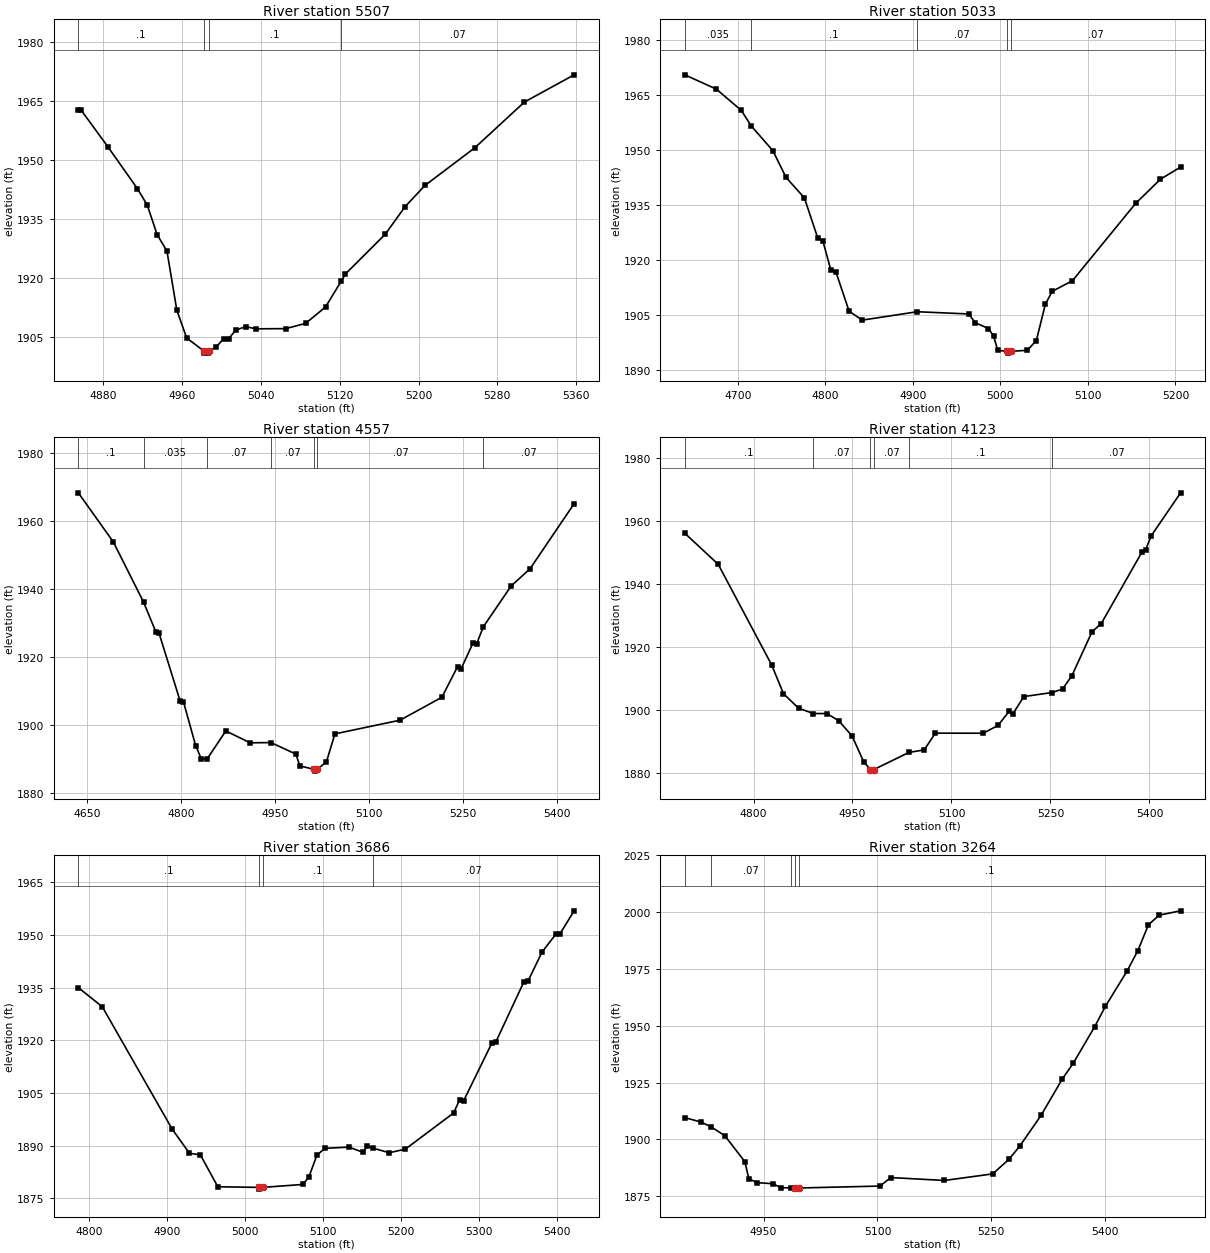
Type RM Length L Ch R = 1 ,5507    ,474,474,474
BEGIN DESCRIPTION:
Stream0464 11.0
END DESCRIPTION:
XS GIS Cut Line= 3
      1905124.97       13968975.        1904975.       13968975.
      1904625.02       13968925.
#Sta/Elev= 30
  4854.5 1962.85    4857 1962.85  4884.5 1953.43  4914.5 1942.79  4924.5 1938.62
  4934.5 1931.12  4944.5 1926.95  4954.5 1911.95  4964.5 1904.88  4982.2 1901.53
  4982.5 1901.03  4986.4 1901.03  4986.8 1901.53  4994.5 1902.58    5002 1904.69
    5007 1904.69  5014.6 1906.91  5024.7 1907.76  5034.8  1907.2  5065.1 1907.25
  5085.3 1908.58  5105.5 1912.74  5121.7 1919.41  5125.7 1921.13  5166.1  1931.2
  5186.3 1938.22  5206.5 1943.61    5257 1953.15  5307.5 1964.79    5358  1971.7
#Mann= 4 ,-1 , 0
  4854.5      .1       0  4982.2     .05       0  4986.8      .1       0
  5121.7     .07       0
Bank Sta=4982.2,4986.8
XS Rating Curve= 0 ,0
Exp/Cntr=0.3,0.1

Type RM Length L Ch R = 1 ,5033    ,476,476,476
BEGIN DESCRIPTION:
Stream0464 10.0
END DESCRIPTION:
XS GIS Cut Line= 3
      1905225.03     13968775.02        1904925.       13968575.
      1904725.04     13968624.99
#Sta/Elev= 30
  4639.3 1970.49  4675.4 1966.59  4703.9 1960.78  4715.1  1956.6    4740 1949.78
    4755 1942.52    4776 1936.92  4791.1  1926.1  4797.1 1925.18  4806.1 1917.34
  4812.1 1916.67  4827.1 1906.02  4842.1 1903.59    4905 1905.88  4963.8 1905.27
  4971.3 1902.88  4986.4  1901.3  4992.4 1899.18  4996.9 1895.35  5007.9 1895.09
  5008.2 1894.59  5012.5 1895.09  5030.8 1895.36  5041.1 1898.02  5051.4 1907.92
  5059.2 1911.43  5082.4 1914.35  5154.5  1935.4  5182.9 1942.02    5206 1945.34
#Mann= 5 ,-1 , 0
  4639.3    .035       0  4715.1      .1       0    4905     .07       0
  5007.9     .05       0  5012.5     .07       0
Bank Sta=5007.9,5012.5
XS Rating Curve= 0 ,0
Exp/Cntr=0.3,0.1

Type RM Length L Ch R = 1 ,4557    ,434,434,434
BEGIN DESCRIPTION:
Stream0464 9.0
END DESCRIPTION:
XS GIS Cut Line= 3
      1905474.96     13968274.99        1905125.       13968175.
      1904724.97     13968024.99
#Sta/Elev= 30
  4636.3 1968.32  4692.2 1953.88  4740.4 1936.21  4759.8 1927.57    4765 1927.15
  4798.8 1907.12    4804 1906.98  4823.5 1894.07  4832.6 1890.14  4842.1 1890.22
  4871.6 1898.37  4910.6 1894.88  4943.7 1894.96  4983.4 1891.57  4989.9  1888.1
    5013 1887.07  5013.4 1886.57  5017.7 1887.07  5032.3 1889.34  5045.7 1897.51
  5149.8 1901.54  5216.5 1908.28  5241.5  1917.3  5246.8 1916.51  5266.4 1924.32
  5271.7 1923.88  5282.7 1929.01  5326.9 1940.94  5357.2 1946.04  5427.5 1965.14
#Mann= 7 ,-1 , 0
  4636.3      .1       0  4740.4    .035       0  4842.1     .07       0
  4943.7     .07       0    5013     .05       0  5017.7     .07       0
  5282.7     .07       0
Bank Sta=5013,5017.7
XS Rating Curve= 0 ,0
Exp/Cntr=0.3,0.1

Type RM Length L Ch R = 1 ,4123    ,437,437,437
BEGIN DESCRIPTION:
Stream0464 8.0
END DESCRIPTION:
XS GIS Cut Line= 3
      1905524.96     13967725.01        1905225.       13967775.
      1904825.01       13967575.
#Sta/Elev= 30
  4695.9 1956.06  4746.5 1946.18  4827.6  1914.2  4845.4 1905.09  4868.2 1900.49
  4890.7 1898.79  4911.3 1898.77    4929 1896.52  4949.3 1891.68    4967 1883.45
  4977.1 1880.99  4977.5 1880.49  4982.3 1880.99  5035.5 1886.42  5058.7 1887.24
  5075.5 1892.55  5148.1 1892.53  5170.5    1895  5187.3 1899.48  5192.9 1898.62
  5209.6 1904.17  5252.5 1905.46  5268.3 1906.56  5282.3 1910.75    5313 1924.77
    5327 1927.38  5388.5 1950.04  5394.1 1950.77  5402.5  1955.2  5447.2 1968.89
#Mann= 6 ,-1 , 0
  4695.9      .1       0  4890.7     .07       0  4977.1     .05       0
  4982.3     .07       0  5035.5      .1       0  5252.5     .07       0
Bank Sta=4977.1,4982.3
XS Rating Curve= 0 ,0
Exp/Cntr=0.3,0.1

Type RM Length L Ch R = 1 ,3686    ,422,422,422
BEGIN DESCRIPTION:
Stream0464 7.0
END DESCRIPTION:
XS GIS Cut Line= 3
      1905474.97     13967474.99        1905275.       13967375.
      1904874.99       13967475.
#Sta/Elev= 30
  4786.2 1934.97  4816.9 1929.53  4906.4 1894.76  4928.7 1887.82  4942.7 1887.38
  4965.1 1878.29  5017.4 1878.12  5017.8 1877.62  5022.7 1878.12  5074.2 1878.95
  5081.9 1881.08  5092.2 1887.31  5102.5 1889.24  5133.5 1889.57  5151.5 1888.08
  5156.7 1889.91  5163.9 1889.29    5185 1887.98  5205.6    1889  5267.5 1899.29
  5275.2 1903.03  5280.4 1902.78  5316.4 1919.12  5321.6 1919.48  5357.7 1936.66
  5362.8 1936.79  5380.9  1945.1  5398.9 1950.26    5404 1950.33  5422.1 1956.83
#Mann= 4 ,-1 , 0
  4786.2      .1       0  5017.4     .05       0  5022.7      .1       0
  5163.9     .07       0
Bank Sta=5017.4,5022.7
XS Rating Curve= 0 ,0
Exp/Cntr=0.3,0.1

Type RM Length L Ch R = 1 ,3264    ,368,368,368
BEGIN DESCRIPTION:
Stream0464 6.0
END DESCRIPTION:
XS GIS Cut Line= 3
        1905525.     13967175.01        1905475.       13967025.
        1905125.       13966675.
#Sta/Elev= 30
  4846.2 1909.56  4867.3 1907.62  4880.7 1905.53  4898.9 1901.59  4925.3 1890.17
  4930.5 1882.71  4941.1 1880.93  4962.2 1880.47  4972.7 1878.73  4985.5 1878.62
    4991 1878.58  4991.5 1878.08  4996.1 1878.08  4996.5 1878.58  5103.3 1879.43
  5117.5 1883.18  5188.2 1881.89  5251.8 1884.79    5273 1891.14  5287.2 1896.92
  5315.4  1910.5  5343.7  1926.7  5357.9  1933.5  5386.2 1949.63  5400.3 1958.58
  5428.6 1973.98  5442.7 1982.88  5456.9 1994.39    5471 1998.68  5499.3 2000.57
#Mann= 5 ,-1 , 0
  4846.2      .1       0  4880.7     .07       0  4985.5      .1       0
    4991     .05       0  4996.5      .1       0
Bank Sta=4991,4996.5
XS Rating Curve= 0 ,0
Exp/Cntr=0.3,0.1

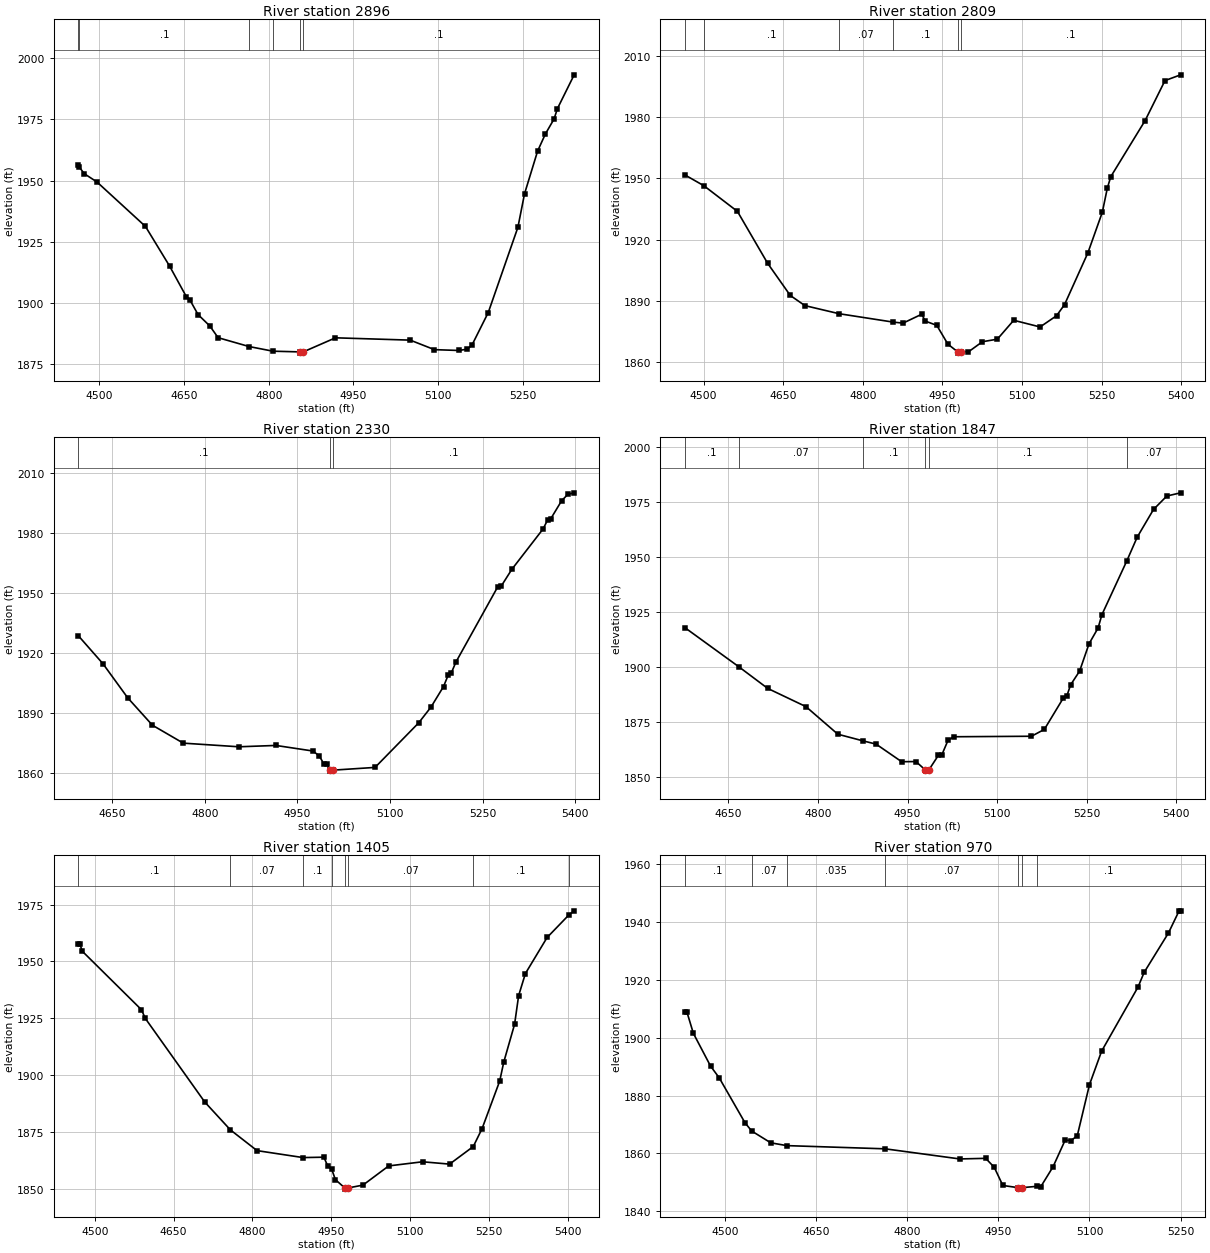
Type RM Length L Ch R = 1 ,2896    ,87,87,87
BEGIN DESCRIPTION:
Mapping XS 463580a2
END DESCRIPTION:
XS GIS Cut Line= 3
      1905913.56     13967181.99      1905683.65     13966858.31
       1905269.3     13966612.11
#Sta/Elev= 30
  4462.5  1956.4  4464.5 1955.42  4472.9 1952.83  4495.6 1949.42  4581.5 1931.29
  4624.2 1915.15  4653.8  1902.7  4659.9 1901.47  4674.7 1895.34  4695.6 1890.68
  4710.3  1885.9  4765.3 1882.28  4807.5 1880.39  4855.7  1880.1  4856.2  1879.6
  4861.2  1880.1  4918.4 1885.85  5050.9  1884.9  5093.8 1881.02  5137.1 1880.68
  5152.2 1881.23  5160.4 1882.92  5189.2 1896.16  5241.8 1930.96  5253.5  1944.6
  5276.7 1962.04  5290.5 1969.02  5305.8 1975.12  5311.9  1979.4  5341.5 1993.15
#Mann= 6 ,-1 , 0
  4462.5     .07       0  4464.5      .1       0  4765.3     .07       0
  4807.5      .1       0  4855.7     .05       0  4861.2      .1       0
Bank Sta=4855.7,4861.2
XS Rating Curve= 0 ,0
Exp/Cntr=0.3,0.1

Type RM Length L Ch R = 1 ,2809    ,479,479,479
BEGIN DESCRIPTION:
Stream0464 5.0
END DESCRIPTION:
XS GIS Cut Line= 3
        1905975.     13967124.99        1905625.       13966725.
      1905275.01     13966525.01
#Sta/Elev= 30
  4464.5 1951.68  4500.4 1946.38  4563.7 1933.81  4620.6 1908.44  4663.3  1892.7
  4690.9 1887.72  4755.4 1883.76  4857.7 1879.64  4875.9 1879.16  4911.1 1883.51
  4917.7 1880.16  4939.5 1878.06  4960.4 1868.87  4979.5 1864.98  4979.9 1864.48
    4985 1864.98  4998.9 1865.06  5025.5 1870.06  5053.6  1871.3  5084.5 1880.55
  5134.2 1877.28  5165.2 1882.77  5180.3 1888.21  5224.2 1913.48  5251.5  1933.4
  5260.9 1945.15  5267.4 1950.77  5332.2 1978.26  5369.6  1997.8  5399.1 2000.62
#Mann= 6 ,-1 , 0
  4464.5     .07       0  4500.4      .1       0  4755.4     .07       0
  4857.7      .1       0  4979.5     .05       0    4985      .1       0
Bank Sta=4979.5,4985
XS Rating Curve= 0 ,0
Exp/Cntr=0.3,0.1

Type RM Length L Ch R = 1 ,2330    ,483,483,483
BEGIN DESCRIPTION:
Stream0464 4.0
END DESCRIPTION:
XS GIS Cut Line= 3
      1906124.99       13966275.        1905725.       13966275.
        1905325.       13966325.
#Sta/Elev= 30
  4595.1 1928.51  4635.1 1914.44  4675.1 1897.41  4715.1  1883.7  4765.1 1874.72
  4855.1  1872.9  4915.1 1873.57  4975.1 1870.78  4985.1 1868.41  4992.6 1864.47
  4997.6 1864.47  5002.4 1861.21  5002.8 1860.71    5008 1861.21  5075.7 1862.57
  5146.3 1884.86  5166.4 1892.82  5186.6 1903.07  5194.1 1908.74  5199.2 1909.88
  5206.7 1915.33  5274.7 1953.15  5279.8 1953.23  5297.4 1961.82  5347.8 1981.96
  5355.4 1986.59  5360.4 1987.14    5378 1996.15  5388.1 1999.34  5398.2 2000.07
#Mann= 3 ,-1 , 0
  4595.1      .1       0  5002.4     .05       0    5008      .1       0
Bank Sta=5002.4,5008
XS Rating Curve= 0 ,0
Exp/Cntr=0.3,0.1

Type RM Length L Ch R = 1 ,1847    ,442,442,442
BEGIN DESCRIPTION:
Stream0464 3.0
END DESCRIPTION:
XS GIS Cut Line= 3
      1906124.96     13965974.98        1905725.       13965825.
      1905374.97     13965624.98
#Sta/Elev= 30
    4577 1918.04  4667.4 1900.26  4715.8 1890.42  4779.9 1882.14  4833.3 1869.61
  4875.5 1866.59  4897.4 1865.11  4940.1 1857.13  4964.1 1857.19  4979.9 1853.35
  4980.4 1852.85  4985.6 1853.35  5001.5 1859.97    5007 1859.97  5017.8 1866.87
  5027.2 1868.46  5157.5 1868.69  5179.1  1871.8  5210.7 1885.98  5216.5 1886.76
    5223 1892.01  5238.1 1898.25  5253.9 1910.67  5269.1 1917.87  5275.5 1923.91
  5317.1 1948.28  5334.6 1959.12  5361.9 1971.69  5384.2 1977.79  5407.3 1979.24
#Mann= 6 ,-1 , 0
    4577      .1       0  4667.4     .07       0  4875.5      .1       0
  4979.9     .05       0  4985.6      .1       0  5317.1     .07       0
Bank Sta=4979.9,4985.6
XS Rating Curve= 0 ,0
Exp/Cntr=0.3,0.1

Type RM Length L Ch R = 1 ,1405    ,435,435,435
BEGIN DESCRIPTION:
Stream0464 2.0
END DESCRIPTION:
XS GIS Cut Line= 3
      1906374.99     13965824.99        1905975.       13965475.
        1905575.       13965375.
#Sta/Elev= 30
  4468.8 1957.61  4472.1 1957.61  4475.9 1954.61  4588.8  1928.8  4596.4  1924.9
  4709.4 1888.15  4758.2 1875.87    4809 1866.73  4896.5 1863.67  4936.2 1863.84
  4943.8 1859.82    4951 1858.59  4958.1 1853.96  4976.1 1850.28  4976.5 1849.78
  4981.8 1850.28  5010.6 1851.55  5059.6    1860    5124 1861.82  5175.5 1860.79
  5220.6 1868.54  5237.4 1876.46  5270.9 1897.38  5278.6 1905.71  5299.2 1922.35
  5306.9 1934.97  5319.8  1944.7  5361.1 1960.56  5402.9 1970.57  5412.6  1972.3
#Mann= 8 ,-1 , 0
  4468.8      .1       0  4758.2     .07       0  4896.5      .1       0
    4951     .07       0  4976.1     .05       0  4981.8     .07       0
  5220.6      .1       0  5402.9     .07       0
Bank Sta=4976.1,4981.8
XS Rating Curve= 0 ,0
Exp/Cntr=0.3,0.1

Type RM Length L Ch R = 1 ,970     ,549,549,549
BEGIN DESCRIPTION:
Stream0464 1.0
END DESCRIPTION:
XS GIS Cut Line= 3
      1906374.99     13965474.99        1905975.       13965075.
      1905724.97       13965075.
#Sta/Elev= 30
  4434.3 1908.91  4437.8 1908.91  4448.4 1901.54  4476.7  1890.2  4490.9 1886.16
  4533.3 1870.62  4544.3 1867.76  4575.7 1863.67  4602.1  1862.7    4764 1861.59
  4886.8 1858.09  4929.3  1858.3  4943.4  1855.2  4957.5 1848.92  4982.9 1848.15
  4983.4 1847.65  4988.7 1848.15  5013.7 1848.62    5020  1848.5    5040 1855.34
    5060 1864.58    5070 1864.47    5080 1866.14    5100 1883.75    5120 1895.37
    5180 1917.59    5190 1922.64    5230 1936.27  5247.5 1943.92    5250 1943.92
#Mann= 7 ,-1 , 0
  4434.3      .1       0  4544.3     .07       0  4602.1    .035       0
    4764     .07       0  4982.9     .05       0  4988.7     .07       0
  5013.7      .1       0
Bank Sta=4982.9,4988.7
XS Rating Curve= 0 ,0
Exp/Cntr=0.3,0.1

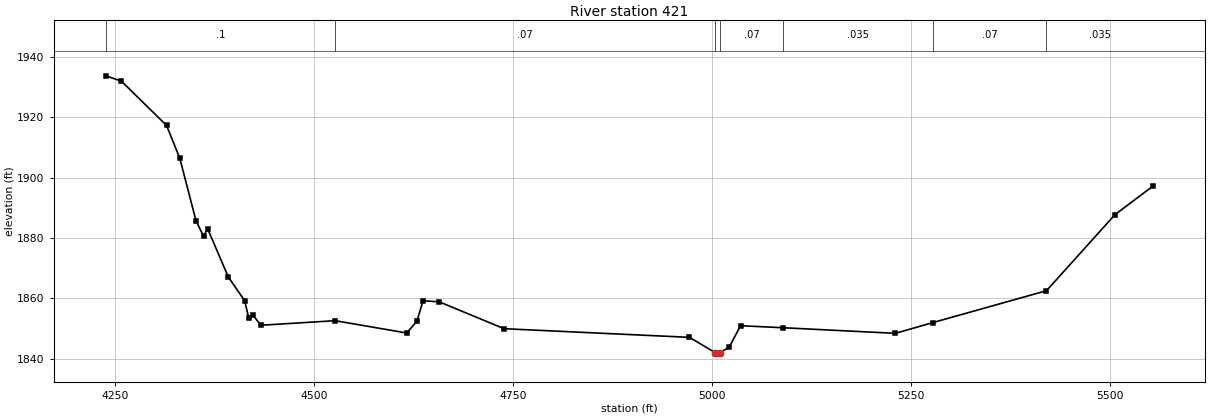
Type RM Length L Ch R = 1 ,421     ,0,0,0
BEGIN DESCRIPTION:
Stream0464 0.0
END DESCRIPTION:
XS GIS Cut Line= 4
      1906544.31     13965346.07      1906437.78     13964799.33
      1906207.17     13964618.71      1905752.62     13964720.24
#Sta/Elev= 30
  4238.2  1933.7  4257.7 1931.92  4314.4 1917.26    4331 1906.42  4351.4 1885.69
  4360.9 1880.52    4366 1883.03  4392.1 1866.98  4412.5 1859.21  4417.6 1853.55
  4422.7 1854.52  4432.9 1851.04  4526.3 1852.55  4616.2 1848.47  4629.1 1852.42
  4636.6 1859.15    4657  1858.8  4738.5  1849.9  4971.4 1847.03  5003.7 1841.97
  5004.2 1841.47  5009.5 1841.97  5021.1 1843.68  5035.6 1850.89  5089.3 1850.21
  5230.2 1848.36  5276.9  1851.9    5420 1862.49  5506.1 1887.71  5553.9 1897.17
#Mann= 7 ,-1 , 0
  4238.2      .1       0  4526.3     .07       0  5003.7     .05       0
  5009.5     .07       0  5089.3    .035       0  5276.9     .07       0
    5420    .035       0
Bank Sta=5003.7,5009.5
XS Rating Curve= 0 ,0
Exp/Cntr=0.3,0.1

Chan Stop Cuts=-1
Use User Specified Reach Order=0
Composite Channel Slope=5