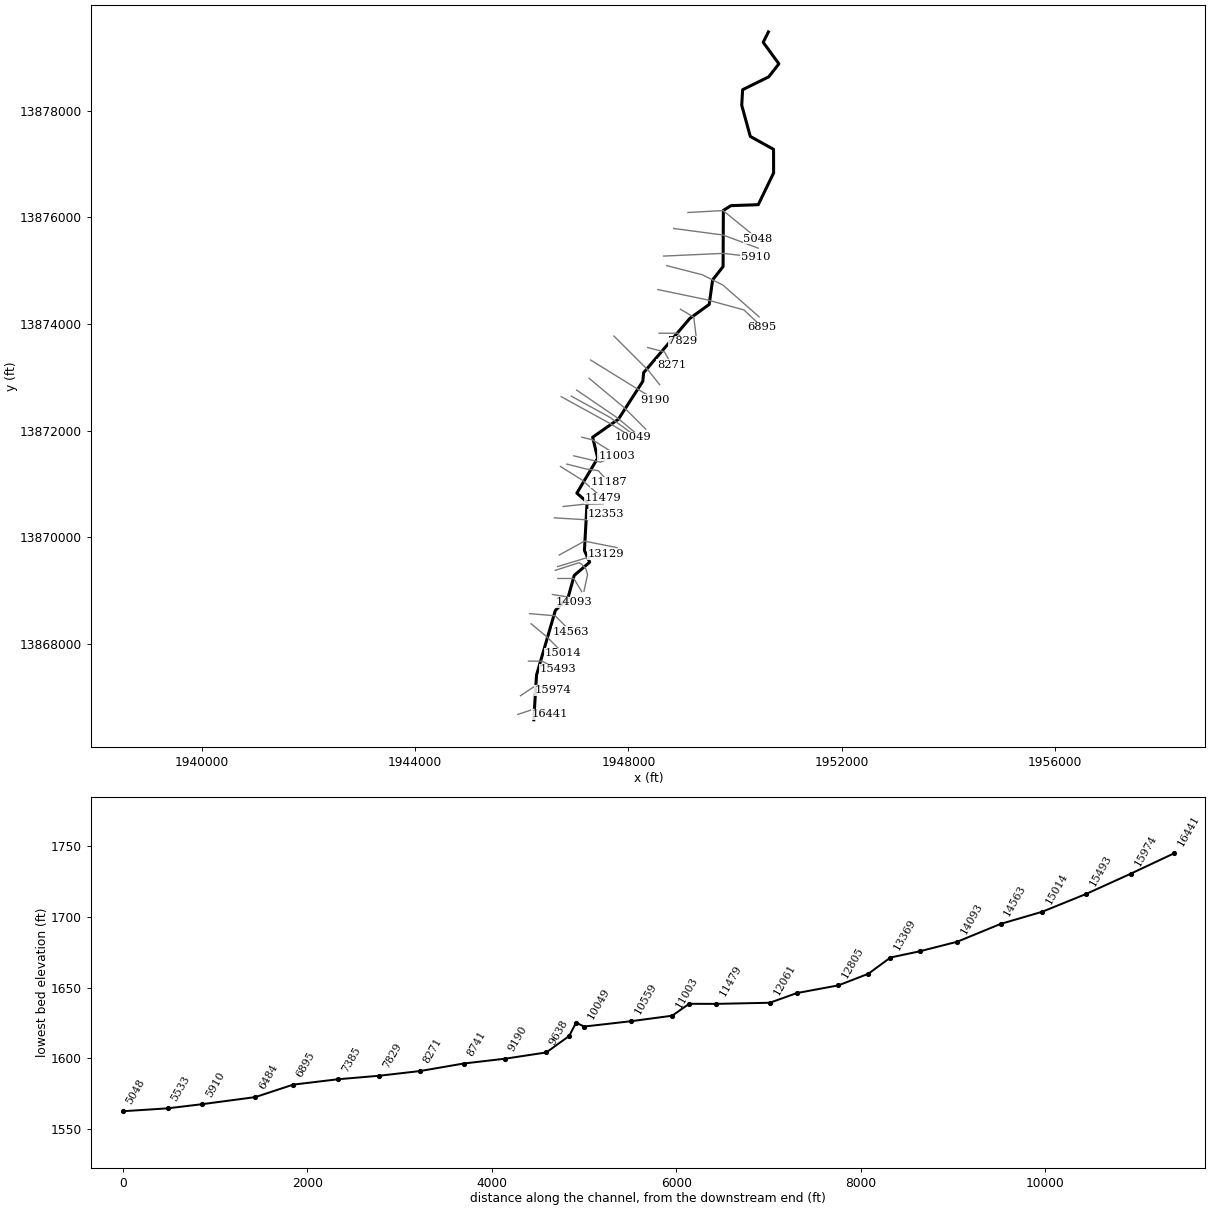
--- Spring Creek 2.prj (project) ---

Proj Title=Spring Creek 2 Base Level Engineering
Current Plan=p01
Default Exp/Contr=0.3,0.1
English Units
Geom File=g01
Flow File=f01
Plan File=p01
Y Axis Title=Elevation
X Axis Title(PF)=Main Channel Distance
X Axis Title(XS)=Station
BEGIN DESCRIPTION:
Spring Creek 2
END DESCRIPTION:
DSS Export Rating Curves= 0
DSS Export Rating Curve Sorted= 0
DSS Export Volume Flow Curves= 0
DXF OffsetX= 0
DXF OffsetY= 0
DXF ScaleX= 1
DXF ScaleY= 10

--- Spring Creek 2.p01 (plan) ---

Plan Title=Multiple Run
Short Identifier=Multiple
Geom File=g01
Flow File=f01
Subcritical Flow
K Sum by GR= 0
Std Step Tol= 0.01
Critical Tol= 0.01
Num of Std Step Trials= 20
Max Error Tol= 0.3
Flow Tol Ratio= 0.001
Split Flow NTrial= 30
Split Flow Tol= 0.02
Split Flow Ratio= 0.02
Log Output Level= 0
Friction Slope Method= 1
Unsteady Friction Slope Method= 2
Unsteady Bridges Friction Slope Method= 1
Parabolic Critical Depth
Global Vel Dist=  1 , 1 , 1
Global Log Level= 0
CheckData=True
Encroach Param= -1, 0, 0, 0
BEGIN DESCRIPTION:
Multiple Run
END DESCRIPTION:

--- Spring Creek 2.f01 (steady flow) ---

Flow Title=Multiple
Number of Profiles=7
Profile Names=10-year,25-year,50-year,1pct_min,100-year,1pct_plu,500-year
River Rch & RM= Spring Creek 2,Reach-1,16441
     915    1542    2135    1434    2861    5708    5060
River Rch & RM= Spring Creek 2,Reach-1,13129
    1802    3182    4544    3138    6262   12494   11741
River Rch & RM= Spring Creek 2,Reach-1,12353
    2580    4622    6661    4634    9245   18447   17600
River Rch & RM= Spring Creek 2,Reach-1,6895
    4025    7376   10795    7615   15193   30314   29754
River Rch & RM= Spring Creek 2,Reach-1,5910
    4819    8860   12993    9174   18304   36520   35919
River Rch & RM= Spring Creek 2,Reach-1,477
    4887    8984   13173    9299   18553   37018   36392
Boundary for River Rch & Prof#=Spring Creek 2,Reach-1,1
Up Type=0
Dn Type=3
Dn Slope=0.005
Boundary for River Rch & Prof#=Spring Creek 2,Reach-1,2
Up Type=0
Dn Type=3
Dn Slope=0.005
Boundary for River Rch & Prof#=Spring Creek 2,Reach-1,3
Up Type=0
Dn Type=3
Dn Slope=0.005
Boundary for River Rch & Prof#=Spring Creek 2,Reach-1,4
Up Type=0
Dn Type=3
Dn Slope=0.005
Boundary for River Rch & Prof#=Spring Creek 2,Reach-1,5
Up Type=0
Dn Type=3
Dn Slope=0.005
Boundary for River Rch & Prof#=Spring Creek 2,Reach-1,6
Up Type=0
Dn Type=3
Dn Slope=0.005
Boundary for River Rch & Prof#=Spring Creek 2,Reach-1,7
Up Type=0
Dn Type=3
Dn Slope=0.005

--- Spring Creek 2.g01 (geometry) ---

Geom Title=Existing Conditions
Program Version=4.10

River Reach=Spring Creek 2  ,Reach-1
Reach XY= 30
        1946225.       13866575.       1946276.2      13867414.5
      1946628.52     13868623.72      1946869.18     13868872.72
      1946983.02     13869281.34      1947273.32     13869531.14
      1947174.79     13869749.91      1947224.34     13870659.17
      1947032.29     13870824.91      1947422.75     13871480.94
      1947328.37     13871873.72       1947811.6      13872211.7
      1948269.52     13872922.56      1948285.35     13873085.12
      1949147.86     13874098.84      1949514.69     13874364.91
      1949578.54     13874823.54        1949775.       13875075.
      1949780.36      13876127.7      1949921.68     13876216.96
      1950434.83     13876235.47      1950722.75     13876830.93
      1950721.49     13877273.75      1950285.63       13877515.
       1950124.8     13878099.92      1950141.41      13878391.8
      1950631.05     13878633.15      1950821.85     13878876.68
      1950527.05     13879280.86        1950625.       13879475.

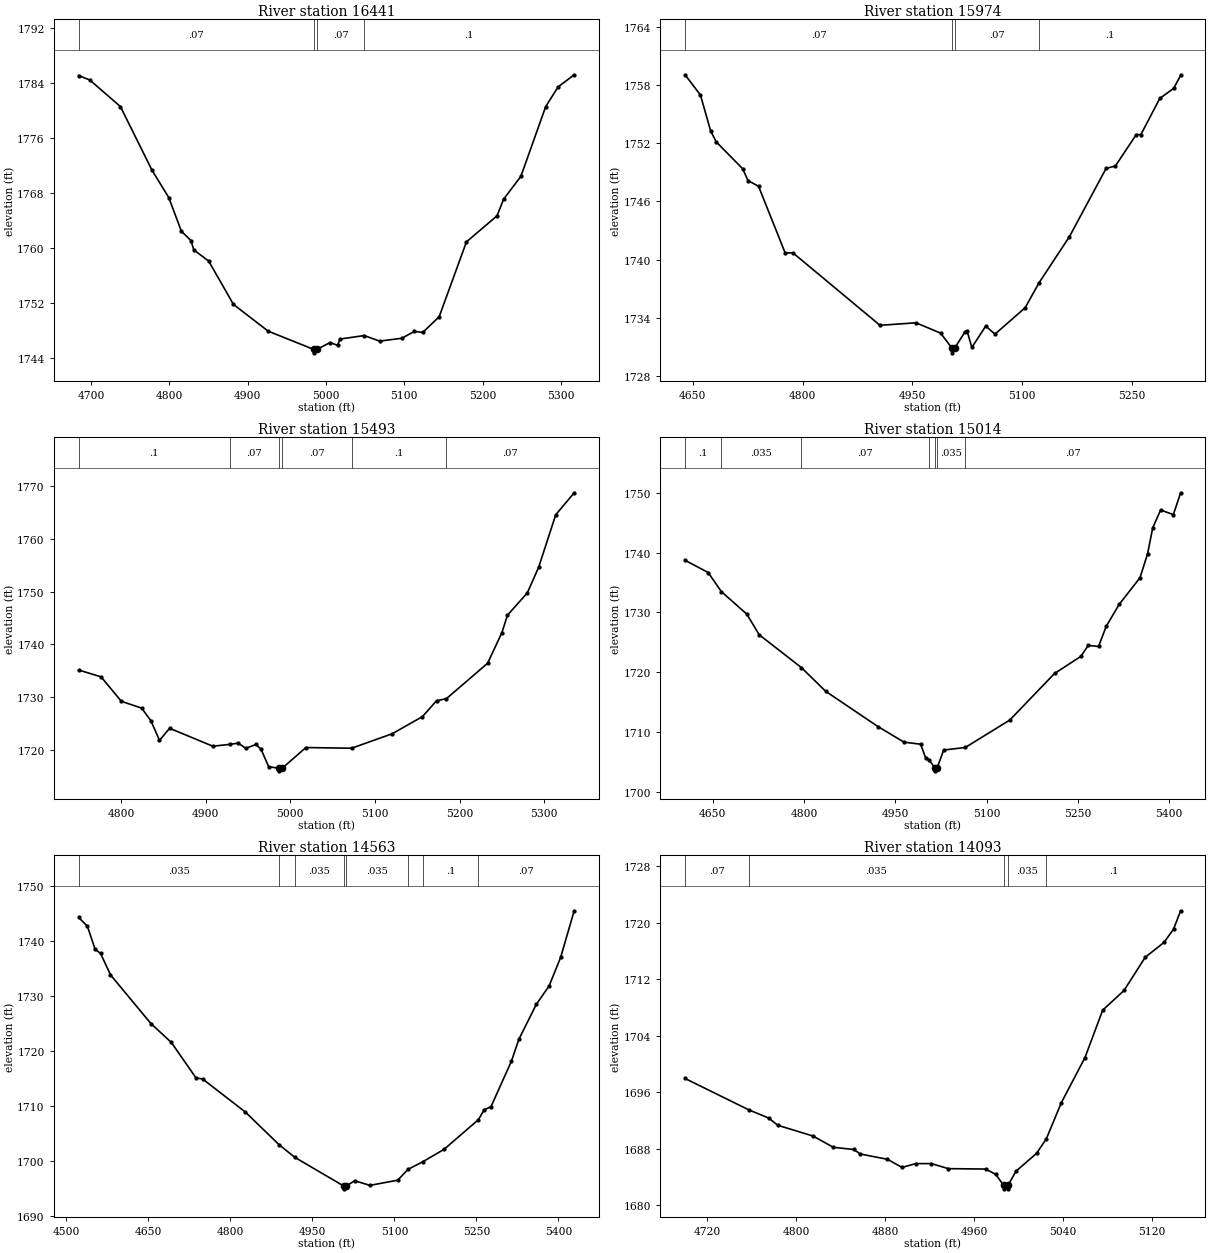
Type RM Length L Ch R = 1 ,16441   ,467,467,467
BEGIN DESCRIPTION:
Spring Creek 2 35.0
END DESCRIPTION:
XS GIS Cut Line= 3
      1945925.03     13866675.01        1946225.       13866775.
      1946524.98     13866675.01
#Sta/Elev= 30
  4684.3 1785.13  4698.5 1784.48  4737.6 1780.61  4777.9 1771.33  4799.3 1767.34
  4815.5 1762.41  4827.7 1761.06  4831.3  1759.7  4850.3 1758.07  4881.9 1751.75
  4926.2 1747.85  4984.3 1745.19  4984.5 1744.69  4988.3 1745.19  5005.2 1746.19
  5014.7 1745.79  5017.9  1746.7  5048.7 1747.21  5068.5  1746.4  5096.9 1746.82
  5112.8 1747.82  5123.4 1747.66  5144.4 1749.95  5179.2 1760.87  5218.3 1764.68
  5226.6 1767.09  5248.7 1770.43  5280.4 1780.61  5296.2 1783.47  5316.7 1785.24
#Mann= 4 ,-1 , 0
  4684.3     .07       0  4984.3     .05       0  4988.3     .07       0
  5048.7      .1       0
Bank Sta=4984.3,4988.3
XS Rating Curve= 0 ,0
Exp/Cntr=0.3,0.1

Type RM Length L Ch R = 1 ,15974   ,481,481,481
BEGIN DESCRIPTION:
Spring Creek 2 34.0
END DESCRIPTION:
XS GIS Cut Line= 3
      1945975.02     13867025.02        1946275.       13867225.
      1946575.04     13867124.99
#Sta/Elev= 30
  4639.5 1759.07  4660.5 1756.97  4674.4 1753.27  4682.1 1752.14  4718.2 1749.37
  4725.4 1748.15  4739.8 1747.57  4776.1  1740.7  4786.9 1740.69  4905.7 1733.22
  4954.9 1733.48  4988.6 1732.41  5003.8 1730.88  5004.1 1730.38  5007.8 1730.88
  5021.8 1732.55  5024.8 1732.59  5031.1 1730.94  5050.1 1733.14  5062.7 1732.31
  5103.9 1735.03  5122.7 1737.58  5164.5 1742.38  5214.5 1749.41  5227.2 1749.66
  5255.6 1752.89    5262  1752.9  5287.8 1756.63  5306.8 1757.67  5316.3 1759.01
#Mann= 4 ,-1 , 0
  4639.5     .07       0  5003.8     .05       0  5007.8     .07       0
  5122.7      .1       0
Bank Sta=5003.8,5007.8
XS Rating Curve= 0 ,0
Exp/Cntr=0.3,0.1

Type RM Length L Ch R = 1 ,15493   ,479,479,479
BEGIN DESCRIPTION:
Spring Creek 2 33.0
END DESCRIPTION:
XS GIS Cut Line= 3
      1946124.98       13867675.        1946375.       13867675.
      1946674.97     13867525.01
#Sta/Elev= 30
  4749.9 1735.19  4776.4 1733.89  4800.4 1729.27  4824.4 1727.99  4835.4 1725.57
  4845.4  1721.9  4857.4 1724.18  4908.4  1720.8  4928.6 1721.15  4938.4 1721.38
  4947.4  1720.4  4959.4 1721.13  4965.4 1720.23  4974.4 1716.92  4986.4 1716.65
  4986.7 1716.15  4990.4 1716.65  5018.4 1720.55  5072.4 1720.42  5120.3 1723.15
  5156.1 1726.39  5172.7 1729.38  5184.3 1729.77    5233 1736.45  5249.8 1742.19
  5256.5 1745.53    5280 1749.75  5293.4 1754.61  5313.5 1764.48  5335.3 1768.64
#Mann= 6 ,-1 , 0
  4749.9      .1       0  4928.6     .07       0  4986.4     .05       0
  4990.4     .07       0  5072.4      .1       0  5184.3     .07       0
Bank Sta=4986.4,4990.4
XS Rating Curve= 0 ,0
Exp/Cntr=0.3,0.1

Type RM Length L Ch R = 1 ,15014   ,451,451,451
BEGIN DESCRIPTION:
Spring Creek 2 32.0
END DESCRIPTION:
XS GIS Cut Line= 3
      1946174.96     13868375.03        1946475.       13868125.
      1946774.98     13867825.02
#Sta/Elev= 30
  4604.4 1738.73  4642.4 1736.69  4663.9 1733.51    4706 1729.71  4726.2 1726.28
  4795.7 1720.77  4835.5 1716.81  4921.4 1710.91  4964.4 1708.29  4991.7 1707.95
  4999.9 1705.66  5005.7 1705.33  5014.9 1703.99  5015.1 1703.49  5018.9 1703.99
  5029.6 1706.97  5065.1  1707.4  5138.2 1711.99    5212  1719.8  5255.2 1722.65
  5267.2 1724.49  5284.2 1724.31  5296.9 1727.69  5318.1 1731.35  5352.4 1735.82
  5364.8 1739.81  5373.3 1744.17  5386.3 1747.15  5407.2 1746.39  5419.2 1750.04
#Mann= 7 ,-1 , 0
  4604.4      .1       0  4663.9    .035       0  4795.7     .07       0
  5005.7    .035       0  5014.9     .05       0  5018.9    .035       0
  5065.1     .07       0
Bank Sta=5014.9,5018.9
XS Rating Curve= 0 ,0
Exp/Cntr=0.3,0.1

Type RM Length L Ch R = 1 ,14563   ,470,470,470
BEGIN DESCRIPTION:
Spring Creek 2 31.0
END DESCRIPTION:
XS GIS Cut Line= 3
      1946144.51     13868565.42        1946625.       13868525.
      1946925.03     13868224.97
#Sta/Elev= 30
  4522.3 1744.24  4538.3 1742.65  4552.5 1738.44  4562.4  1737.7  4580.5 1733.82
  4654.4 1724.96  4691.9 1721.52    4737 1715.07  4749.1 1714.88  4827.4 1708.86
  4889.1 1702.92  4917.7 1700.64  5007.4 1695.41  5007.7 1694.91  5011.4 1695.41
  5027.5 1696.38  5055.1 1695.54    5106 1696.48  5124.9 1698.45  5152.5 1699.87
  5190.8 1702.09  5253.5 1707.47    5264 1709.25  5276.7 1709.86  5313.9 1718.08
  5327.6 1722.08  5359.5 1728.44  5382.8 1731.76    5404 1736.96  5428.8 1745.45
#Mann= 8 ,-1 , 0
  4522.3    .035       0  4889.1     .07       0  4917.7    .035       0
  5007.4    .035       0  5011.4    .035       0  5124.9     .07       0
  5152.5      .1       0  5253.5     .07       0
Bank Sta=5007.4,5011.4
XS Rating Curve= 0 ,0
Exp/Cntr=0.3,0.1

Type RM Length L Ch R = 1 ,14093   ,408,408,408
BEGIN DESCRIPTION:
Spring Creek 2 30.0
END DESCRIPTION:
XS GIS Cut Line= 3
      1946575.01       13868925.        1946875.       13868875.
      1946975.04     13868774.96
#Sta/Elev= 30
  4700.3 1697.96  4757.7 1693.51  4775.5 1692.36  4783.6 1691.34  4815.4 1689.81
  4833.6 1688.22  4851.9 1687.91  4857.9 1687.27  4882.3 1686.52  4895.4 1685.37
  4907.7 1685.91  4921.8 1685.91    4937  1685.2  4970.5 1685.14  4979.6  1684.4
  4986.7 1682.84    4987 1682.34  4990.5 1682.34  4990.7 1682.84  4997.8 1684.83
  5016.4 1687.37  5025.1 1689.41  5038.7 1694.56  5059.9 1700.93  5075.8 1707.63
    5095 1710.42    5114 1715.11    5131 1717.23  5139.5  1719.1  5145.9  1721.7
#Mann= 5 ,-1 , 0
  4700.3     .07       0  4757.7    .035       0  4986.7    .035       0
  4990.7    .035       0  5025.1      .1       0
Bank Sta=4986.7,4990.7
XS Rating Curve= 0 ,0
Exp/Cntr=0.3,0.1

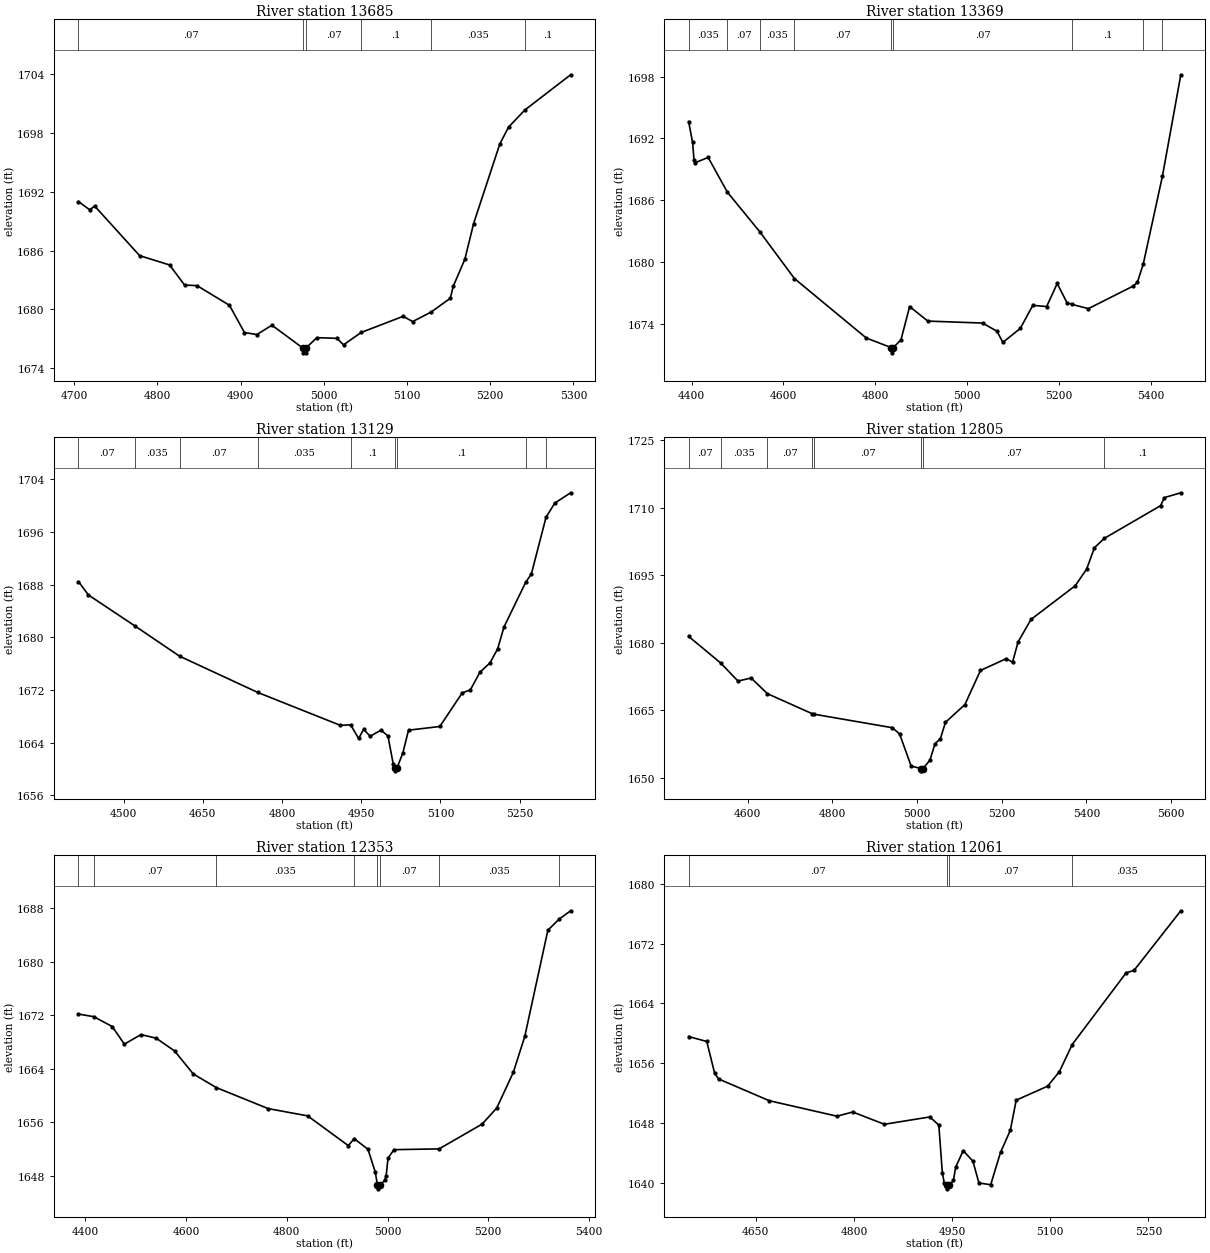
Type RM Length L Ch R = 1 ,13685   ,316,316,316
BEGIN DESCRIPTION:
Spring Creek 2 29.0
END DESCRIPTION:
XS GIS Cut Line= 3
      1946675.04       13869225.        1946975.       13869225.
        1947125.     13868975.01
#Sta/Elev= 30
  4705.1    1691  4718.6 1690.16  4724.6 1690.54  4778.6 1685.48  4814.6 1684.53
  4832.6 1682.48  4847.6 1682.42  4886.6 1680.41  4904.6 1677.63  4919.6 1677.43
  4937.6 1678.38  4974.6 1676.06  4974.8 1675.56  4978.3 1675.56  4978.6 1676.06
  4991.6 1677.11  5015.6 1677.04  5023.7 1676.38  5044.9 1677.64  5095.4 1679.29
  5106.7 1678.75  5128.9 1679.72    5152 1681.13  5155.5 1682.35  5169.5 1685.12
    5180 1688.76  5211.5 1696.88    5222  1698.6  5241.5 1700.34  5296.6 1703.94
#Mann= 6 ,-1 , 0
  4705.1     .07       0  4974.6     .05       0  4978.6     .07       0
  5044.9      .1       0  5128.9    .035       0  5241.5      .1       0
Bank Sta=4974.6,4978.6
XS Rating Curve= 0 ,0
Exp/Cntr=0.3,0.1

Type RM Length L Ch R = 1 ,13369   ,240,240,240
BEGIN DESCRIPTION:
Spring Creek 2 28.1
END DESCRIPTION:
XS GIS Cut Line= 6
      1946629.33      13869377.6      1947064.26     13869518.23
      1947104.63     13869506.51      1947195.77     13869419.28
      1947233.53     13869300.79      1947165.82     13868985.65
#Sta/Elev= 30
  4393.4 1693.63    4402  1691.6  4405.1 1689.92  4408.3 1689.65  4435.9 1690.15
  4477.8 1686.78    4549  1682.9  4623.8  1678.4  4780.3 1672.63  4835.1 1671.69
  4835.3 1671.19  4839.1 1671.69    4856 1672.47  4874.7 1675.68  4914.5 1674.27
  5033.7 1674.08  5065.2 1673.28  5077.8  1672.2  5115.8 1673.56  5143.1  1675.8
  5173.2 1675.68  5196.2 1677.92  5217.5 1676.05  5228.4 1675.89  5264.2 1675.48
  5361.7 1677.67  5370.9 1678.04  5383.7 1679.82  5425.4 1688.34  5465.4 1698.17
#Mann= 9 ,-1 , 0
  4393.4    .035       0  4477.8     .07       0    4549    .035       0
  4623.8     .07       0  4835.1     .05       0  4839.1     .07       0
  5228.4      .1       0  5383.7    .035       0  5425.4      .1       0
Bank Sta=4835.1,4839.1
XS Rating Curve= 0 ,0
Exp/Cntr=0.3,0.1

Type RM Length L Ch R = 1 ,13129   ,324,324,324
BEGIN DESCRIPTION:
Spring Creek 2 28.0
END DESCRIPTION:
XS GIS Cut Line= 3
      1946673.25     13869447.77      1947235.87     13869619.52
      1947574.91     13869674.99
#Sta/Elev= 30
  4414.7 1688.48  4433.5 1686.44  4521.8 1681.72    4606 1677.14  4754.3 1671.62
  4910.6 1666.62    4930  1666.7  4945.1 1664.63  4954.5 1666.01    4967 1664.97
  4987.4 1665.89  5000.6 1665.02  5010.7 1660.72  5014.1 1660.21  5014.4 1659.71
  5018.1 1660.21  5028.9 1662.44  5039.6 1665.89  5098.8 1666.45  5141.4 1671.57
  5156.6 1672.01  5174.8  1674.7  5193.8 1676.11  5208.3 1678.25  5220.4 1681.59
  5261.7 1688.41  5272.1 1689.61    5300 1698.27  5316.5  1700.4  5346.5 1701.97
#Mann= 9 ,-1 , 0
  4414.7     .07       0  4521.8    .035       0    4606     .07       0
  4754.3    .035       0    4930      .1       0  5014.1     .05       0
  5018.1      .1       0  5261.7     .07       0    5300      .1       0
Bank Sta=5014.1,5018.1
XS Rating Curve= 0 ,0
Exp/Cntr=0.3,0.1

Type RM Length L Ch R = 1 ,12805   ,452,452,452
BEGIN DESCRIPTION:
Spring Creek 2 27.0
END DESCRIPTION:
XS GIS Cut Line= 3
      1946702.57     13869664.62        1947175.       13869925.
      1947785.43     13869804.19
#Sta/Elev= 30
    4461 1681.42  4536.4 1675.53  4577.5 1671.49  4608.4 1672.18    4647 1668.69
  4751.7 1664.28  4757.6 1664.12  4941.6 1661.13  4958.8 1659.77  4986.2  1652.6
  5010.2 1652.04  5010.4 1651.54  5014.2 1652.04  5030.5 1653.91  5042.7  1657.6
    5055 1658.63  5067.2 1662.32  5113.1 1666.27  5149.8 1673.85  5210.9 1676.49
  5225.5 1675.67  5238.5 1680.17    5269 1685.19  5373.6 1692.69  5400.5  1696.4
  5418.9 1701.15  5442.4 1703.23  5574.9 1710.48    5584 1712.28  5622.7 1713.35
#Mann= 8 ,-1 , 0
    4461     .07       0  4536.4    .035       0    4647     .07       0
  4751.7    .035       0  4757.6     .07       0  5010.2     .05       0
  5014.2     .07       0  5442.4      .1       0
Bank Sta=5010.2,5014.2
XS Rating Curve= 0 ,0
Exp/Cntr=0.3,0.1

Type RM Length L Ch R = 1 ,12353   ,292,292,292
BEGIN DESCRIPTION:
Spring Creek 2 26.0
END DESCRIPTION:
XS GIS Cut Line= 3
      1946612.56     13870361.95        1947225.       13870325.
      1947574.95     13870424.98
#Sta/Elev= 30
  4386.1 1672.18  4416.4 1671.79  4453.2 1670.32  4477.2 1667.69  4510.3 1669.11
  4540.3 1668.58  4576.9 1666.68  4614.2 1663.23  4659.8  1661.2  4762.7 1658.06
  4841.3 1656.97    4922 1652.53  4933.8 1653.56  4961.1 1651.98  4975.7 1648.55
    4980 1646.57  4980.3 1646.07  4984.4 1646.57  4994.1 1647.34  4997.1 1647.94
  5000.9 1650.65  5012.7 1651.92  5102.4 1652.04  5187.7 1655.74  5216.8 1658.14
  5249.8 1663.48  5272.6 1668.86  5318.4 1684.71  5340.9 1686.37  5363.6 1687.61
#Mann= 8 ,-1 , 0
  4386.1      .1       0  4416.4     .07       0  4659.8    .035       0
  4933.8     .07       0    4980     .05       0  4984.4     .07       0
  5102.4    .035       0  5340.9     .07       0
Bank Sta=4980,4984.4
XS Rating Curve= 0 ,0
Exp/Cntr=0.3,0.1

Type RM Length L Ch R = 1 ,12061   ,582,582,582
BEGIN DESCRIPTION:
Spring Creek 2 25.0
END DESCRIPTION:
XS GIS Cut Line= 3
      1946774.97       13870575.      1947161.72     13870615.97
      1947524.99       13870625.
#Sta/Elev= 30
  4547.3 1659.58    4575 1658.93  4587.1 1654.67  4593.1 1653.92  4670.5 1651.02
    4774 1648.95  4798.2 1649.51  4846.5 1647.87  4915.9 1648.85  4929.7 1647.77
  4935.1  1641.4    4938 1640.06  4941.6 1639.75  4941.9 1639.25    4946 1639.75
    4952 1640.37  4955.5 1642.14    4967 1644.35  4981.9 1642.93    4991 1640.03
    5009  1639.8    5024 1644.11    5039 1647.06    5048 1651.09    5096 1652.96
  5114.1 1654.91  5133.6 1658.52  5216.1  1668.1  5228.1 1668.42  5299.6 1676.38
#Mann= 4 ,-1 , 0
  4547.3     .07       0  4941.6     .05       0    4946     .07       0
  5133.6    .035       0
Bank Sta=4941.6,4946
XS Rating Curve= 0 ,0
Exp/Cntr=0.3,0.1

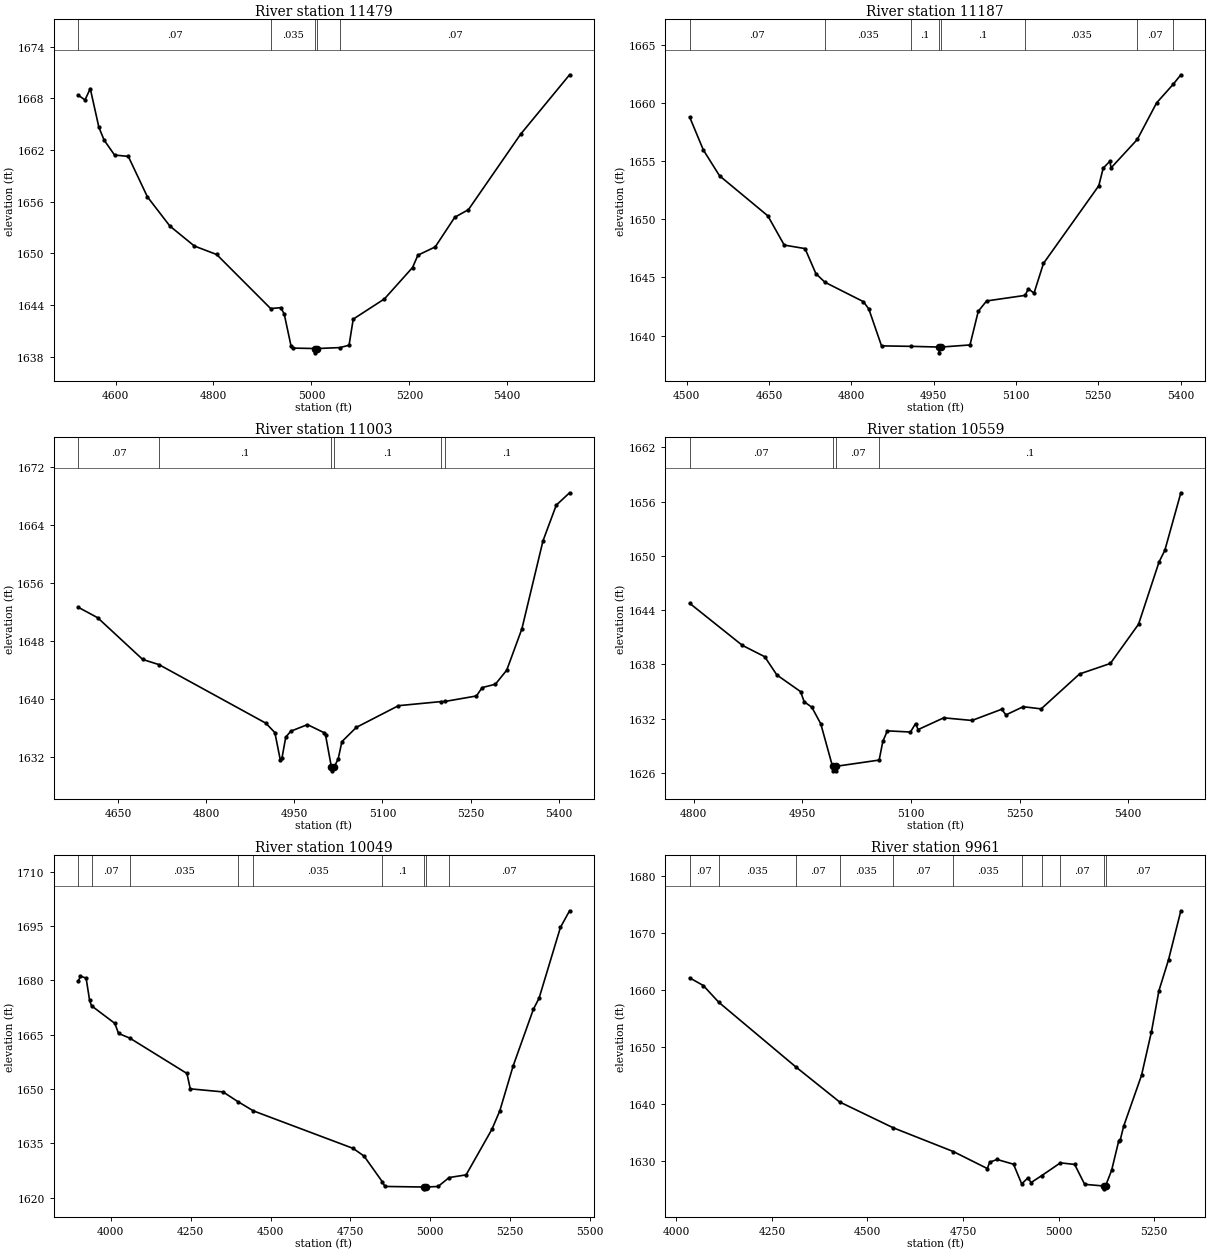
Type RM Length L Ch R = 1 ,11479   ,292,292,292
BEGIN DESCRIPTION:
Spring Creek 2 24.0
END DESCRIPTION:
XS GIS Cut Line= 3
      1946725.02     13871324.99        1947125.       13871075.
      1947525.01     13870724.99
#Sta/Elev= 30
  4524.1 1668.34  4537.6  1667.8  4548.3 1669.12  4565.9 1664.63  4576.6 1663.14
  4597.9 1661.41    4626 1661.25    4665 1656.56  4710.9 1653.17    4761 1650.85
  4806.5 1649.87  4916.7  1643.6  4937.6  1643.7  4944.5 1642.95  4958.6  1639.2
  4962.2 1639.01  5007.5 1638.96  5007.8 1638.46    5012 1638.96  5058.1 1639.07
  5076.9 1639.34  5085.4 1642.37  5149.2 1644.72  5206.6 1648.36  5217.5 1649.79
  5252.9 1650.75  5292.8 1654.19  5320.7 1655.07  5427.1 1663.81  5527.3 1670.72
#Mann= 5 ,-1 , 0
  4524.1     .07       0  4916.7    .035       0  5007.5    .035       0
    5012    .035       0  5058.1     .07       0
Bank Sta=5007.5,5012
XS Rating Curve= 0 ,0
Exp/Cntr=0.3,0.1

Type RM Length L Ch R = 1 ,11187   ,184,184,184
BEGIN DESCRIPTION:
Mapping XS 6639028b
END DESCRIPTION:
XS GIS Cut Line= 4
      1946844.38     13871369.89      1947217.59     13871276.33
      1947434.43     13871247.04       1947630.5     13871031.29
#Sta/Elev= 30
  4505.5 1658.81  4530.4 1655.98  4559.9 1653.76  4647.9 1650.31  4677.8 1647.79
  4715.7 1647.49  4735.5 1645.33    4752 1644.59    4822 1642.92  4831.9 1642.29
  4855.1 1639.11  4907.9 1639.07  4959.5 1639.01  4959.9 1638.51  4964.1 1639.01
  5016.3 1639.19  5031.4 1642.09  5046.6 1642.98  5116.9 1643.46  5122.6 1644.03
    5133 1643.65  5150.2 1646.21    5251  1652.9  5259.1 1654.42  5271.2 1655.01
  5273.4 1654.44  5321.2 1656.89  5356.4 1660.04  5386.4 1661.63  5400.6 1662.46
#Mann= 8 ,-1 , 0
  4505.5     .07       0    4752    .035       0  4907.9      .1       0
  4959.5     .05       0  4964.1      .1       0  5116.9    .035       0
  5321.2     .07       0  5386.4      .1       0
Bank Sta=4959.5,4964.1
XS Rating Curve= 0 ,0
Exp/Cntr=0.3,0.1

Type RM Length L Ch R = 1 ,11003   ,444,444,444
BEGIN DESCRIPTION:
Spring Creek 2 23.0
END DESCRIPTION:
XS GIS Cut Line= 3
        1946975.       13871525.      1947474.28     13871406.27
      1947774.99       13871525.
#Sta/Elev= 30
  4582.2 1652.64    4615 1651.21  4691.7 1645.46  4719.4 1644.75  4901.4 1636.68
  4916.8 1635.38    4926 1631.62  4928.9 1631.88  4935.3 1634.74  4943.8 1635.57
  4972.3 1636.48    5000 1635.39  5003.1 1635.04  5013.1 1630.61  5013.5 1630.11
  5017.7 1630.61  5024.7 1631.77  5030.9 1634.13  5055.5  1636.1  5127.3 1639.09
  5199.3 1639.65  5206.4 1639.67  5260.1 1640.43  5269.8 1641.58  5292.4 1642.05
  5311.7 1643.99  5337.5 1649.68  5373.4  1661.8    5396 1666.72  5418.7 1668.43
#Mann= 6 ,-1 , 0
  4582.2     .07       0  4719.4      .1       0  5013.1     .05       0
  5017.7      .1       0  5199.3    .035       0  5206.4      .1       0
Bank Sta=5013.1,5017.7
XS Rating Curve= 0 ,0
Exp/Cntr=0.3,0.1

Type RM Length L Ch R = 1 ,10559   ,510,510,510
BEGIN DESCRIPTION:
Spring Creek 2 22.0
END DESCRIPTION:
XS GIS Cut Line= 3
      1947124.97     13871875.01        1947325.       13871825.
      1947725.01     13871574.99
#Sta/Elev= 30
  4794.7 1644.76  4867.4 1640.11  4898.2 1638.86    4915 1636.84  4947.7    1635
  4952.7 1633.88  4963.3 1633.27  4975.6 1631.44  4991.8 1626.74  4992.1 1626.24
  4996.2 1626.24  4996.6 1626.74  5056.2 1627.43  5061.3 1629.51  5067.5 1630.66
  5099.4 1630.53  5106.4 1631.46    5110  1630.8  5145.3  1632.1  5184.3 1631.81
  5225.4 1633.05  5231.1 1632.42    5255 1633.33  5279.8 1633.09  5332.8 1636.95
  5375.3 1638.11  5414.2 1642.45  5442.5 1649.33  5450.5 1650.62  5472.6 1656.98
#Mann= 4 ,-1 , 0
  4794.7     .07       0  4991.8     .05       0  4996.6     .07       0
  5056.2      .1       0
Bank Sta=4991.8,4996.6
XS Rating Curve= 0 ,0
Exp/Cntr=0.3,0.1

Type RM Length L Ch R = 1 ,10049   ,88,88,88
BEGIN DESCRIPTION:
Spring Creek 2 21.0
END DESCRIPTION:
XS GIS Cut Line= 3
      1946738.65     13872634.88      1947648.46     13872135.22
      1948074.97     13871875.02
#Sta/Elev= 30
  3898.4 1679.85  3904.8  1681.2  3922.5 1680.65  3933.5 1674.48  3939.4 1673.01
  4012.3 1668.16  4024.1 1665.37  4059.7 1664.06  4238.2 1654.31  4248.5 1650.07
  4351.2 1649.22  4397.1 1646.57  4446.2 1643.98  4758.5 1633.62  4792.7 1631.49
  4849.8  1624.4  4857.7 1623.11  4980.4 1622.95  4980.8 1622.45  4985.4 1622.95
  5024.3  1623.1    5059 1625.57  5112.1 1626.31    5193 1638.91  5217.6    1644
  5259.4 1656.41  5322.8 1672.07  5340.6 1675.13  5407.3 1694.64    5436 1699.25
#Mann= 9 ,-1 , 0
  3898.4    .035       0  3939.4     .07       0  4059.7    .035       0
  4397.1     .07       0  4446.2    .035       0  4849.8      .1       0
  4980.4     .05       0  4985.4      .1       0    5059     .07       0
Bank Sta=4980.4,4985.4
XS Rating Curve= 0 ,0
Exp/Cntr=0.3,0.1

Type RM Length L Ch R = 1 ,9961    ,75,75,75
BEGIN DESCRIPTION:
Spring Creek 2 20.5
END DESCRIPTION:
XS GIS Cut Line= 3
      1946928.69     13872644.11      1947649.19     13872249.14
      1948022.48     13871975.68
#Sta/Elev= 30
  4035.1 1662.18  4070.7 1660.84    4111 1657.91  4312.7 1646.56  4427.1 1640.42
  4567.6 1635.88  4724.5 1631.72  4813.4 1628.74  4819.6 1629.85  4838.9 1630.33
  4881.9  1629.5  4903.3 1626.04  4919.1 1627.08  4928.1 1626.29  4955.9 1627.51
  5004.5 1629.74  5041.8 1629.46  5067.9 1625.97  5117.4 1625.68  5117.8 1625.18
  5122.5 1625.68  5138.5 1628.44  5157.1 1633.61  5160.9 1633.72  5169.8 1636.14
  5216.6 1645.08  5242.7 1652.76  5262.1 1659.92  5287.3 1665.37  5319.5 1673.95
#Mann= 11 ,-1 , 0
  4035.1     .07       0    4111    .035       0  4312.7     .07       0
  4427.1    .035       0  4567.6     .07       0  4724.5    .035       0
  4903.3     .07       0  4955.9      .1       0  5004.5     .07       0
  5117.4     .05       0  5122.5     .07       0
Bank Sta=5117.4,5122.5
XS Rating Curve= 0 ,0
Exp/Cntr=0.3,0.1

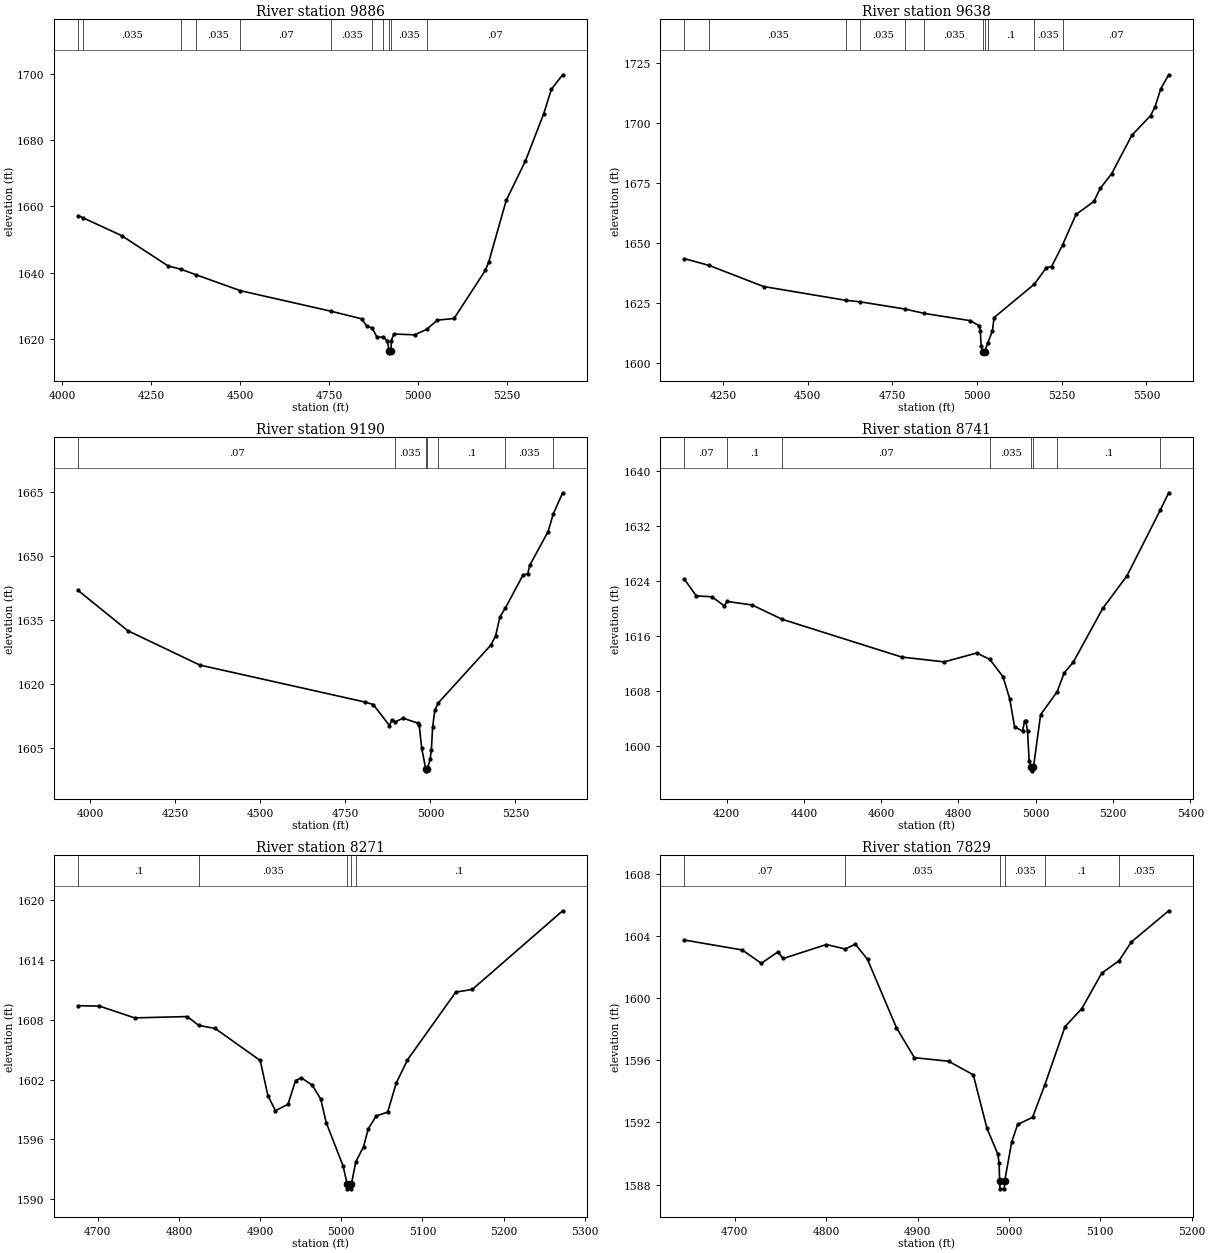
Type RM Length L Ch R = 1 ,9886    ,248,248,248
BEGIN DESCRIPTION:
Spring Creek 2 20.1
END DESCRIPTION:
XS GIS Cut Line= 3
      1947028.42     13872757.65      1947793.71     13872236.93
      1948128.81     13871956.81
#Sta/Elev= 30
  4044.7 1657.24  4058.6 1656.55    4167 1651.18  4297.6 1642.03  4334.5 1640.99
  4377.2 1639.32  4501.3 1634.54  4756.8 1628.32  4842.2 1626.04  4856.4 1623.81
  4871.4 1623.29  4885.2 1620.49    4903 1620.57  4914.5 1619.33  4919.2 1616.28
  4919.6 1615.78  4924.3 1616.28  4925.3 1619.49  4932.6 1621.46  4990.7 1621.22
  5024.5 1622.86  5054.8 1625.65  5101.7 1626.15  5190.1 1640.75  5199.4 1643.27
  5248.4 1661.82  5302.4 1673.73  5353.8 1687.97  5375.4 1695.38  5407.1 1699.74
#Mann= 11 ,-1 , 0
  4044.7     .07       0  4058.6    .035       0  4334.5     .07       0
  4377.2    .035       0  4501.3     .07       0  4756.8    .035       0
  4871.4     .07       0    4903    .035       0  4919.2    .035       0
  4924.3    .035       0  5024.5     .07       0
Bank Sta=4919.2,4924.3
XS Rating Curve= 0 ,0
Exp/Cntr=0.3,0.1

Type RM Length L Ch R = 1 ,9638    ,448,448,448
BEGIN DESCRIPTION:
Spring Creek 2 20.0
END DESCRIPTION:
XS GIS Cut Line= 3
      1947261.37     13872979.81        1947925.       13872425.
      1948325.01     13872024.99
#Sta/Elev= 30
    4135 1643.48  4208.9 1640.61  4369.8 1631.81  4613.4 1626.04  4655.3 1625.43
  4787.3 1622.42  4844.4  1620.6  4979.7 1617.58  5007.1 1615.37  5009.5 1613.24
    5012 1607.04  5017.3 1604.66  5017.7 1604.16  5022.4 1604.66  5031.5 1608.28
  5045.3 1613.41  5050.2 1618.87  5169.4 1632.85  5204.7 1639.73  5219.9 1640.14
  5252.2 1649.12    5292 1661.86  5344.7 1667.28  5363.5 1672.72  5397.4 1678.91
  5456.8 1694.87    5512 1703.08  5525.4 1706.74  5542.3 1714.28  5565.7 1720.13
#Mann= 11 ,-1 , 0
    4135     .07       0  4208.9    .035       0  4613.4     .07       0
  4655.3    .035       0  4787.3     .07       0  4844.4    .035       0
  5017.3    .035       0  5022.4    .035       0  5031.5      .1       0
  5169.4    .035       0  5252.2     .07       0
Bank Sta=5017.3,5022.4
XS Rating Curve= 0 ,0
Exp/Cntr=0.3,0.1

Type RM Length L Ch R = 1 ,9190    ,449,449,449
BEGIN DESCRIPTION:
Spring Creek 2 19.0
END DESCRIPTION:
XS GIS Cut Line= 3
      1947290.07     13873322.33        1948175.       13872775.
       1948504.5     13872577.06
#Sta/Elev= 30
  3963.9 1641.98  4110.2 1632.54  4321.9  1624.5  4806.7 1615.86  4831.9 1615.26
  4879.2 1610.35  4886.2 1611.57  4896.6 1611.19  4919.1 1612.07  4963.8 1610.89
    4967 1610.36  4974.4    1605    4986 1600.24  4986.4 1599.74  4991.1 1600.24
  4999.1 1602.43  5002.7 1604.73  5006.4 1609.94  5012.8 1613.96  5023.1 1615.65
  5177.6 1629.17  5191.6 1631.34  5204.5 1635.84  5220.6  1637.9  5272.1 1645.57
    5286 1645.86  5291.8 1647.83  5345.6 1655.69  5361.5 1659.95  5388.8 1664.83
#Mann= 7 ,-1 , 0
  3963.9     .07       0  4896.6    .035       0    4986    .035       0
  4991.1    .035       0  5023.1      .1       0  5220.6    .035       0
  5361.5     .07       0
Bank Sta=4986,4991.1
XS Rating Curve= 0 ,0
Exp/Cntr=0.3,0.1

Type RM Length L Ch R = 1 ,8741    ,470,470,470
BEGIN DESCRIPTION:
Spring Creek 2 18.0
END DESCRIPTION:
XS GIS Cut Line= 4
      1947728.25     13873771.75        1948275.       13873225.
        1948375.       13873125.      1948585.47     13872859.17
#Sta/Elev= 30
  4090.2 1624.27  4121.7 1621.79  4162.3 1621.66  4194.1 1620.34  4201.3 1620.98
  4265.9 1620.47  4343.7 1618.39  4652.7  1612.9    4763 1612.19  4847.2 1613.48
    4881 1612.56  4915.4 1610.02  4932.7 1606.79  4945.1 1602.76  4965.9 1602.12
  4970.9 1603.57  4974.4 1603.54  4978.7 1602.08  4982.9 1597.81  4988.8 1596.84
  4989.2 1596.34    4994 1596.84  5012.5 1604.51  5055.2 1607.84  5073.7 1610.61
  5096.7 1612.12  5173.2 1619.96    5236 1624.72  5322.5 1634.32  5343.9 1636.79
#Mann= 8 ,-1 , 0
  4090.2     .07       0  4201.3      .1       0  4343.7     .07       0
    4881    .035       0  4988.8    .035       0    4994    .035       0
  5055.2      .1       0  5322.5    .035       0
Bank Sta=4988.8,4994
XS Rating Curve= 0 ,0
Exp/Cntr=0.3,0.1

Type RM Length L Ch R = 1 ,8271    ,442,442,442
BEGIN DESCRIPTION:
Spring Creek 2 17.0
END DESCRIPTION:
XS GIS Cut Line= 3
      1948361.05     13873555.88        1948675.       13873475.
      1948808.98     13873237.36
#Sta/Elev= 30
  4675.8  1609.4  4702.1 1609.36  4745.4 1608.18  4810.5 1608.31  4824.3 1607.43
  4844.6 1607.12  4900.2 1603.91  4909.6  1600.4  4918.9 1598.88  4934.4 1599.52
  4943.7  1601.9  4950.6 1602.18  4964.3 1601.44  4974.7 1600.05  4981.5 1597.68
  5002.3 1593.34  5007.2 1591.55  5007.6 1591.05  5012.2 1591.05  5012.6 1591.55
    5018 1593.77  5027.5 1595.27  5033.3 1597.07  5043.1 1598.35  5057.2 1598.74
  5067.8 1601.65  5081.5 1603.96  5141.1 1610.76  5161.5 1611.03  5272.8 1618.91
#Mann= 5 ,-1 , 0
  4675.8      .1       0  4824.3    .035       0  5007.2    .035       0
  5012.6    .035       0    5018      .1       0
Bank Sta=5007.2,5012.6
XS Rating Curve= 0 ,0
Exp/Cntr=0.3,0.1

Type RM Length L Ch R = 1 ,7829    ,444,444,444
BEGIN DESCRIPTION:
Spring Creek 2 16.0
END DESCRIPTION:
XS GIS Cut Line= 3
      1948574.96       13873825.        1948925.       13873825.
      1949024.99     13873675.02
#Sta/Elev= 30
  4644.5 1603.74    4708  1603.1    4729 1602.24    4747 1602.97    4753 1602.55
  4800.2 1603.45  4820.8 1603.16  4831.9 1603.47  4845.2 1602.49  4876.9 1598.09
  4896.5 1596.17  4933.9 1595.94  4960.9 1595.07  4975.9 1591.63  4987.9 1589.95
  4989.2 1589.38  4989.8 1588.23  4990.2 1587.73  4994.8 1587.73  4995.3 1588.23
    5003 1590.74  5009.5 1591.87  5025.8 1592.33  5039.2 1594.41  5061.4 1598.17
  5079.8 1599.33  5101.5 1601.61  5120.4  1602.4  5133.9 1603.61  5174.8 1605.62
#Mann= 6 ,-1 , 0
  4644.5     .07       0  4820.8    .035       0  4989.8    .035       0
  4995.3    .035       0  5039.2      .1       0  5120.4    .035       0
Bank Sta=4989.8,4995.3
XS Rating Curve= 0 ,0
Exp/Cntr=0.3,0.1

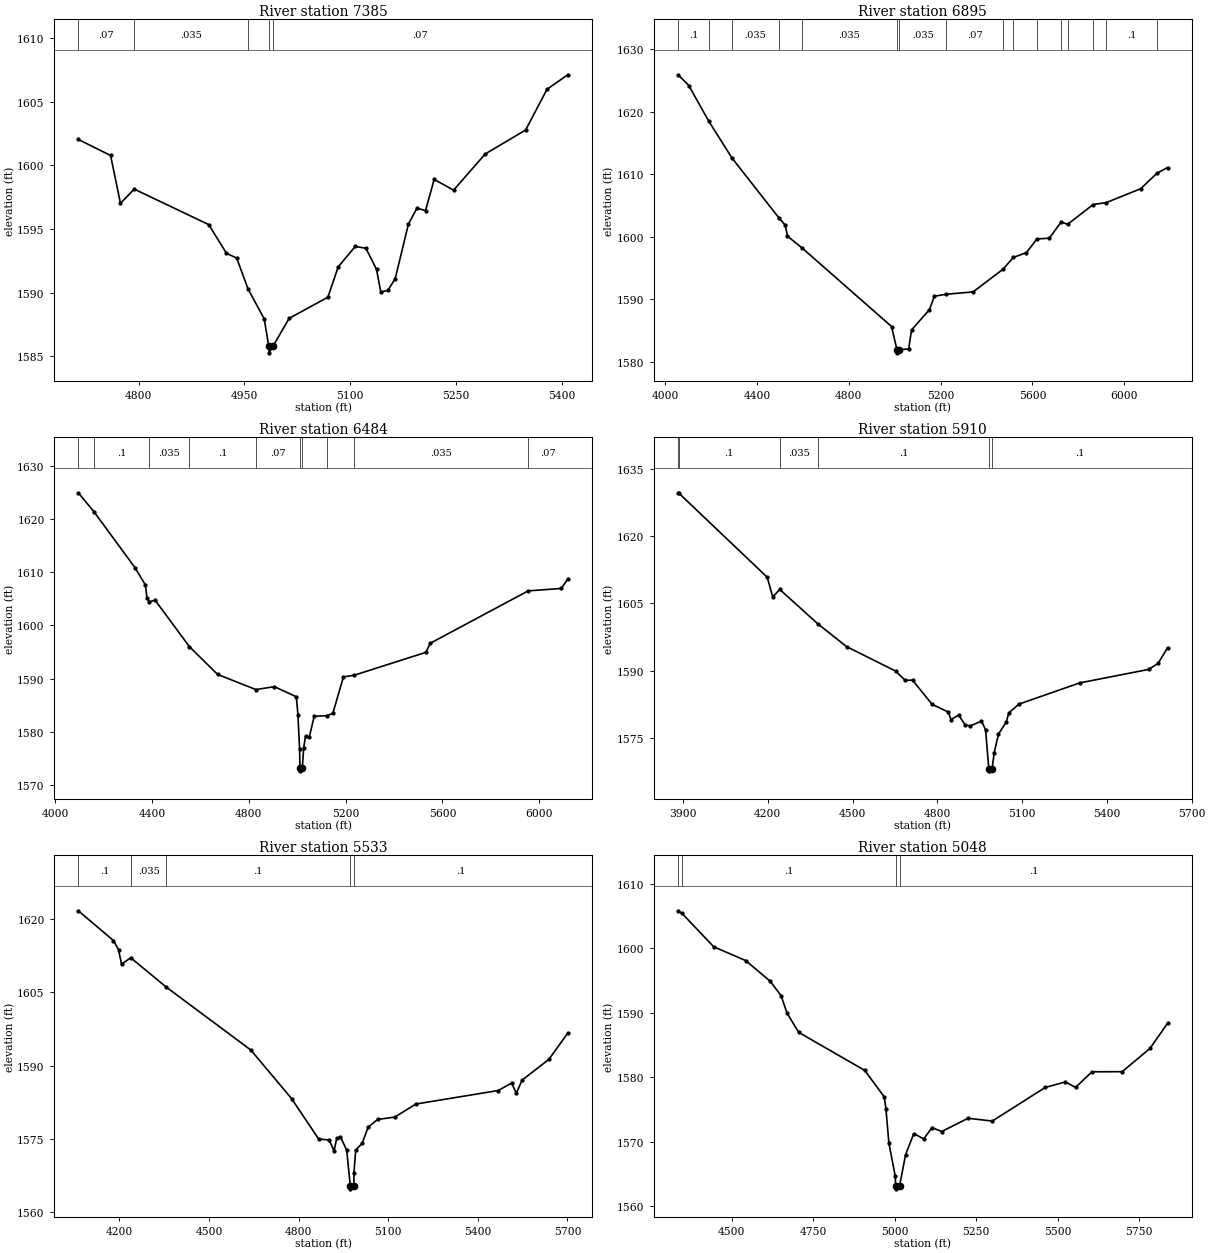
Type RM Length L Ch R = 1 ,7385    ,490,490,490
BEGIN DESCRIPTION:
Spring Creek 2 15.0
END DESCRIPTION:
XS GIS Cut Line= 3
      1948975.03     13874274.98        1949225.       13874125.
        1949275.     13873725.02
#Sta/Elev= 30
  4714.2 1602.03    4760 1600.77    4774 1597.01  4793.5 1598.13  4899.3 1595.34
  4924.4 1593.09    4939 1592.71    4955 1590.29    4978 1587.94  4984.5 1585.77
    4985 1585.27  4990.3 1585.77  5013.4 1587.98  5068.4 1589.64    5083 1592.02
  5107.2 1593.63  5122.4 1593.48  5137.4 1591.82  5143.4 1590.05  5153.5 1590.17
  5163.9  1591.1  5182.7 1595.39  5194.8 1596.64  5206.9 1596.44  5219.2 1598.89
  5246.8 1598.05  5291.6 1600.89    5349 1602.77  5379.3 1605.97  5408.8 1607.11
#Mann= 5 ,-1 , 0
  4714.2     .07       0  4793.5    .035       0    4955     .07       0
  4984.5     .05       0  4990.3     .07       0
Bank Sta=4984.5,4990.3
XS Rating Curve= 0 ,0
Exp/Cntr=0.3,0.1

Type RM Length L Ch R = 1 ,6895    ,411,411,411
BEGIN DESCRIPTION:
Spring Creek 2 14.0
END DESCRIPTION:
XS GIS Cut Line= 4
      1948550.75     13874643.31      1949461.91       13874454.
      1950164.94     13874262.35      1950509.69      13873938.5
#Sta/Elev= 30
  4056.2 1625.95  4102.9 1624.23  4190.3 1618.49  4291.6  1612.6  4494.3  1603.1
  4523.5 1601.86  4532.7 1600.12  4595.6 1598.26  4986.2 1585.66  5009.5 1581.95
    5010 1581.45  5018.9 1581.95  5060.8 1582.08  5073.3 1585.12    5151 1588.35
  5172.8 1590.51    5225 1590.83  5341.2  1591.2  5472.6 1594.85  5516.3 1596.71
  5573.9  1597.5  5619.3 1599.67  5673.4  1599.8  5724.8 1602.37  5753.8 1602.03
  5864.2 1605.18  5921.2 1605.49  6071.4 1607.71  6142.9 1610.21  6188.5  1611.1
#Mann= 16 ,-1 , 0
  4056.2      .1       0  4190.3     .07       0  4291.6    .035       0
  4494.3     .07       0  4595.6    .035       0  5009.5    .035       0
  5018.9    .035       0    5225     .07       0  5472.6      .1       0
  5516.3    .035       0  5619.3      .1       0  5724.8    .035       0
  5753.8      .1       0  5864.2     .07       0  5921.2      .1       0
  6142.9    .035       0
Bank Sta=5009.5,5018.9
XS Rating Curve= 0 ,0
Exp/Cntr=0.3,0.1

Type RM Length L Ch R = 1 ,6484    ,574,574,574
BEGIN DESCRIPTION:
Spring Creek 2 13.0
END DESCRIPTION:
XS GIS Cut Line= 4
      1948718.87     13875091.74      1949385.06     13874921.23
        1949775.       13874725.      1950449.82     13874132.37
#Sta/Elev= 30
  4095.6 1624.93  4159.8 1621.39  4329.3 1610.87  4372.7  1607.6  4378.9 1605.19
  4388.7 1604.44    4413 1604.72  4554.3 1596.01  4670.8 1590.78  4829.2 1587.92
  4905.6 1588.47  4996.3 1586.57    5003 1583.22  5009.7 1576.75  5011.7 1573.14
  5012.2 1572.64  5021.2 1573.14  5026.5 1576.88  5034.3 1579.16    5050 1579.02
  5070.1 1582.88    5125 1583.03  5147.4 1583.49    5191 1590.31  5234.6 1590.61
  5531.5 1594.92  5549.7 1596.63  5954.2 1606.48  6091.4 1606.94  6117.9 1608.74
#Mann= 10 ,-1 , 0
  4095.6     .07       0  4159.8      .1       0  4388.7    .035       0
  4554.3      .1       0  4829.2     .07       0  5011.7     .05       0
  5021.2     .07       0    5125      .1       0  5234.6    .035       0
  5954.2     .07       0
Bank Sta=5011.7,5021.2
XS Rating Curve= 0 ,0
Exp/Cntr=0.3,0.1

Type RM Length L Ch R = 1 ,5910    ,377,377,377
BEGIN DESCRIPTION:
Spring Creek 2 12.0
END DESCRIPTION:
XS GIS Cut Line= 3
      1948658.74     13875271.39      1949778.44     13875322.33
      1950385.57     13875251.57
#Sta/Elev= 30
  3882.5  1629.7  3884.6 1629.65    4198 1610.85  4217.4 1606.44  4242.2 1608.14
  4377.5 1600.43  4478.7 1595.38  4651.9 1589.93  4686.3 1587.86  4712.2  1587.9
  4781.1 1582.52  4839.1 1580.76  4848.1 1579.11  4875.1 1580.08  4899.1 1577.88
  4917.1 1577.69  4956.2 1578.77  4970.7 1576.83    4982 1568.16  4982.5 1567.66
  4993.8 1568.16  5001.2 1571.74  5016.3 1575.86  5043.5 1578.51  5053.4 1580.64
  5088.8 1582.55  5303.3 1587.27  5547.9 1590.29  5581.1 1591.63  5614.6  1595.1
#Mann= 6 ,-1 , 0
  3882.5     .07       0  3884.6      .1       0  4242.2    .035       0
  4377.5      .1       0    4982     .05       0  4993.8      .1       0
Bank Sta=4982,4993.8
XS Rating Curve= 0 ,0
Exp/Cntr=0.3,0.1

Type RM Length L Ch R = 1 ,5533    ,485,485,485
BEGIN DESCRIPTION:
Spring Creek 2 11.0
END DESCRIPTION:
XS GIS Cut Line= 3
      1948846.96     13875788.91      1949775.04     13875666.33
      1950432.45     13875420.81
#Sta/Elev= 30
  4063.1 1621.75  4180.5 1615.65  4197.7 1613.78  4207.7 1610.79  4238.5 1612.11
  4357.4 1606.09  4640.4 1593.18  4776.6 1583.22  4867.4 1574.92  4902.4 1574.72
  4918.8 1572.49  4927.9 1575.04    4940  1575.4  4961.2 1572.63  4973.4  1565.2
  4973.9  1564.7  4985.3  1565.2  4985.4    1568  4991.4 1572.66  5013.4 1574.07
  5032.6 1577.32  5064.7 1578.94  5122.3 1579.42  5192.7  1582.1  5468.2 1584.87
    5513  1586.4    5529 1584.33  5548.2    1587  5637.9 1591.27    5701 1596.65
#Mann= 5 ,-1 , 0
  4063.1      .1       0  4238.5    .035       0  4357.4      .1       0
  4973.4     .05       0  4985.3      .1       0
Bank Sta=4973.4,4985.3
XS Rating Curve= 0 ,0
Exp/Cntr=0.3,0.1

Type RM Length L Ch R = 1 ,5048    ,465,465,465
BEGIN DESCRIPTION:
Spring Creek 2 10.0
END DESCRIPTION:
XS GIS Cut Line= 3
       1949115.9     13876089.09        1949775.       13876125.
      1950427.21     13875594.19
#Sta/Elev= 30
    4336 1605.83  4348.1 1605.42  4445.3 1600.24  4543.7 1598.09  4618.8 1594.87
  4651.9 1592.65  4669.9 1589.96    4706 1586.95  4908.4 1581.05  4968.2 1576.94
  4973.4 1575.11  4982.4 1569.79  5001.6 1564.72  5003.4 1563.16  5003.9 1562.66
  5015.4 1563.16  5033.7 1567.97  5058.9 1571.25  5089.2 1570.41  5114.8 1572.16
  5144.6 1571.56  5225.3 1573.62  5299.5 1573.18  5461.9  1578.4  5523.8 1579.26
  5554.8  1578.4  5605.1 1580.83  5697.9 1580.85    5783 1584.45    5837 1588.35
#Mann= 4 ,-1 , 0
    4336    .035       0  4348.1      .1       0  5003.4     .05       0
  5015.4      .1       0
Bank Sta=5003.4,5015.4
XS Rating Curve= 0 ,0
Exp/Cntr=0.3,0.1