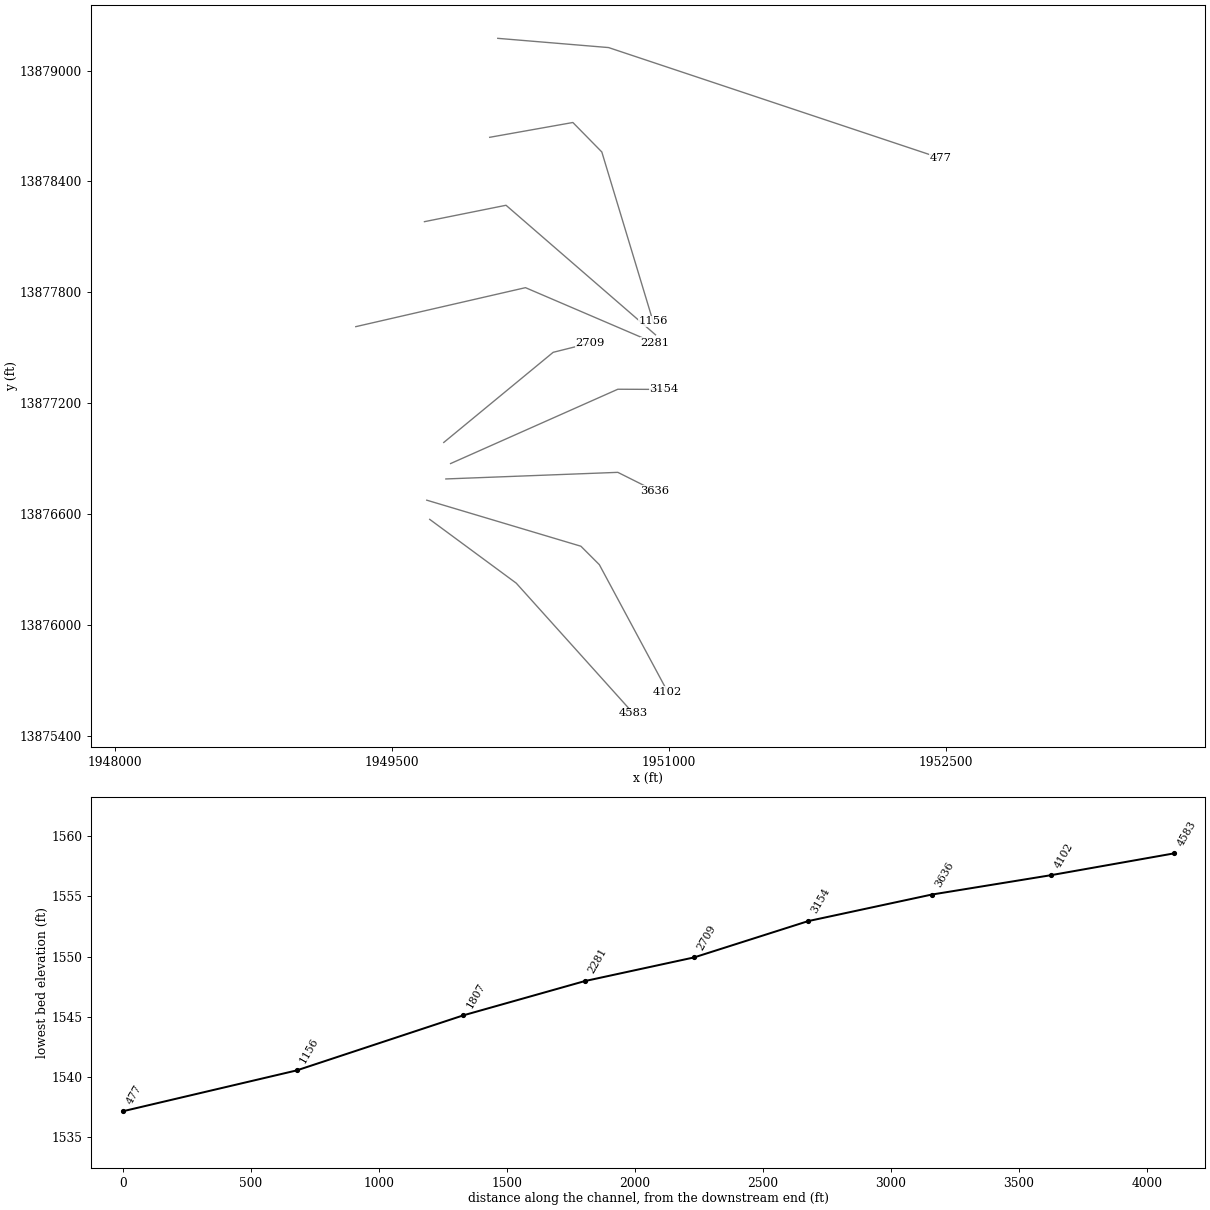
HEC-RAS study Spring Creek 2.prj: Spring Creek 2 Base Level Engineering

--- Spring Creek 2.g01 (geometry) --- (continued)

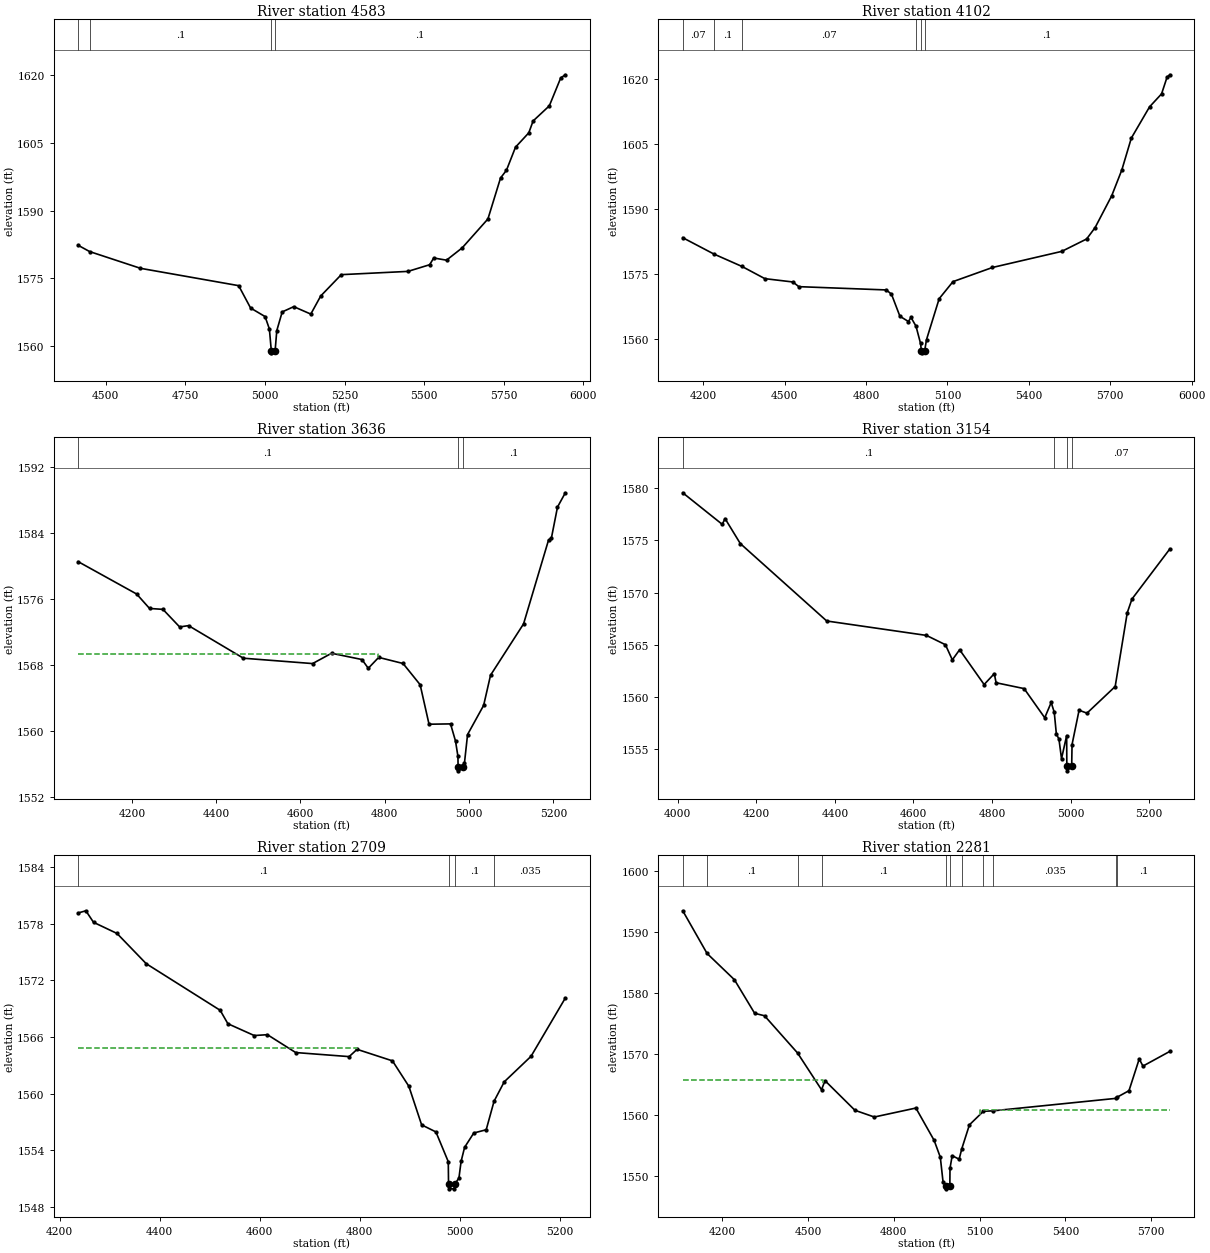
Type RM Length L Ch R = 1 ,4583    ,481,481,481
BEGIN DESCRIPTION:
Spring Creek 2 9.0
END DESCRIPTION:
XS GIS Cut Line= 3
       1949706.5     13876570.41        1950175.       13876225.
      1950808.93     13875519.96
#Sta/Elev= 30
  4413.5 1582.32  4449.4 1580.94  4609.1 1577.24  4917.5 1573.41    4955 1568.47
  5000.5 1566.58    5014 1563.85    5020 1559.07  5020.5 1558.57  5032.1 1559.07
  5037.3 1563.48  5054.3 1567.61  5090.6 1568.77  5144.1 1567.13  5175.3 1571.13
  5239.9 1575.84  5449.2 1576.56  5517.4 1578.03  5530.3 1579.52  5570.4 1579.04
  5619.7 1581.76  5700.5 1588.14  5740.1 1597.18  5758.8 1598.91  5787.2    1604
  5828.9 1607.17  5842.5 1609.79  5893.4 1613.13  5929.3 1619.31  5943.7 1619.99
#Mann= 4 ,-1 , 0
  4413.5     .07       0  4449.4      .1       0    5020     .05       0
  5032.1      .1       0
Bank Sta=5020,5032.1
XS Rating Curve= 0 ,0
Exp/Cntr=0.3,0.1

Type RM Length L Ch R = 1 ,4102    ,466,466,466
BEGIN DESCRIPTION:
Spring Creek 2 8.0
END DESCRIPTION:
XS GIS Cut Line= 4
      1949690.39     13876674.36        1950525.       13876425.
        1950625.       13876325.      1950995.58     13875635.34
#Sta/Elev= 30
  4124.3 1583.36    4239 1579.59  4342.9 1576.71  4426.9  1573.9  4530.2 1573.13
  4552.1 1572.05  4874.6 1571.29  4893.6 1570.31  4924.7 1565.21    4956    1564
  4965.6 1564.93    4984 1562.92  5000.6 1558.97  5003.9 1557.26  5004.4 1556.76
    5016 1557.26  5022.7 1559.81  5069.4 1569.27  5120.3 1573.21  5265.8 1576.48
  5521.2  1580.2  5612.8 1583.06  5643.9 1585.67  5705.2 1593.03  5742.6 1599.01
  5777.6 1606.37  5844.8 1613.59  5889.1 1616.59  5909.5 1620.48  5919.7    1621
#Mann= 6 ,-1 , 0
  4124.3     .07       0    4239      .1       0  4342.9     .07       0
    4984      .1       0  5003.9     .05       0    5016      .1       0
Bank Sta=5003.9,5016
XS Rating Curve= 0 ,0
Exp/Cntr=0.3,0.1

Type RM Length L Ch R = 1 ,3636    ,482,482,482
BEGIN DESCRIPTION:
Spring Creek 2 7.0
END DESCRIPTION:
XS GIS Cut Line= 3
      1949793.85     13876789.27        1950725.       13876825.
      1950924.97     13876725.02
#Sta/Elev= 30
  4072.8  1580.5  4211.4 1576.58    4242 1574.83  4273.8 1574.72  4313.4 1572.59
  4334.5 1572.75  4464.6  1568.8  4628.7 1568.15  4673.7  1569.4  4745.8 1568.64
  4760.8 1567.58  4785.5  1568.9  4843.3 1568.16  4883.8 1565.59  4904.9  1560.8
  4955.9 1560.84  4967.7 1558.76  4973.5 1556.89  4973.8 1555.65  4974.3 1555.15
  4986.1 1555.65  4988.9 1556.08  4996.3 1559.55  5034.4 1563.08  5050.8 1566.74
  5129.1 1572.96  5188.3 1583.11  5195.1 1583.35  5209.6 1587.12  5228.2 1588.85
#Mann= 3 ,-1 , 0
  4072.8      .1       0  4973.8     .05       0  4986.1      .1       0
#XS Ineff= 2 , 0
         4784.62 1569.25
Permanent Ineff=
       F       F
Bank Sta=4973.8,4986.1
XS Rating Curve= 0 ,0
Exp/Cntr=0.3,0.1

Type RM Length L Ch R = 1 ,3154    ,445,445,445
BEGIN DESCRIPTION:
Spring Creek 2 6.0
END DESCRIPTION:
XS GIS Cut Line= 3
      1949819.44      13876872.6        1950725.       13877275.
      1950973.95     13877274.08
#Sta/Elev= 30
  4012.8 1579.56  4113.3 1576.54  4120.5 1577.09  4159.3  1574.7  4379.3 1567.29
  4633.1 1565.91  4681.4 1565.02    4699 1563.57  4717.5 1564.54  4779.9 1561.21
  4805.8 1562.25  4810.4 1561.38  4881.7 1560.82  4934.2 1558.03  4950.6 1559.49
  4958.4 1558.56  4963.8 1556.46  4970.3    1556  4976.9 1554.11    4990 1556.33
  4990.4 1553.45  4990.9 1552.95  5002.8 1553.45  5003.7 1555.47  5021.6 1558.75
  5041.7 1558.47  5113.5 1561.02  5144.2 1568.08  5156.2 1569.39  5252.7 1574.19
#Mann= 4 ,-1 , 0
  4012.8      .1       0  4958.4     .07       0  4990.4     .05       0
  5002.8     .07       0
Bank Sta=4990.4,5002.8
XS Rating Curve= 0 ,0
Exp/Cntr=0.3,0.1

Type RM Length L Ch R = 1 ,2709    ,428,428,428
BEGIN DESCRIPTION:
Spring Creek 2 5.0
END DESCRIPTION:
XS GIS Cut Line= 3
      1949782.51     13876986.85        1950375.       13877475.
      1950574.96     13877524.99
#Sta/Elev= 30
  4237.3 1579.13  4252.6 1579.36  4267.9 1578.14  4314.9 1576.96  4373.3 1573.76
  4521.1 1568.83  4536.5 1567.41  4589.2 1566.16  4615.5 1566.25  4672.1 1564.36
  4778.9 1563.93  4794.8  1564.7  4865.5 1563.48  4898.3 1560.79  4923.8 1556.71
  4952.4 1555.96  4977.1 1552.81  4977.6 1550.44  4978.1 1549.94  4989.5 1549.94
    4990 1550.44  4998.4 1551.08  5002.7 1552.84  5009.7 1554.33  5028.1 1555.85
  5052.9 1556.19  5068.6 1559.21  5088.9 1561.26  5142.5 1563.96  5211.1 1570.13
#Mann= 4 ,-1 , 0
  4237.3      .1       0  4977.6     .05       0    4990      .1       0
  5068.6    .035       0
#XS Ineff= 2 , 0
         4794.61 1564.84
Permanent Ineff=
       F       F
Bank Sta=4977.6,4990
XS Rating Curve= 0 ,0
Exp/Cntr=0.3,0.1

Type RM Length L Ch R = 1 ,2281    ,474,474,474
BEGIN DESCRIPTION:
Spring Creek 2 4.0
END DESCRIPTION:
XS GIS Cut Line= 3
      1949306.24     13877613.87        1950225.       13877825.
      1950925.02     13877524.99
#Sta/Elev= 30
  4061.5  1593.5  4146.6 1586.51  4242.3 1582.21  4313.1 1576.71  4347.6 1576.31
  4463.1 1570.22    4547  1564.2  4559.3 1565.68    4664 1560.83  4731.7 1559.73
  4877.2  1561.2    4941 1555.91  4962.6 1553.15  4972.3 1549.07  4983.6 1548.47
  4984.1 1547.97    4996 1548.47  4996.5 1551.33  5004.2  1553.4  5028.5 1552.82
  5037.9 1554.55  5064.5 1558.45  5113.3 1560.67  5146.6 1560.74  5578.4 1562.79
  5581.4 1562.98  5622.7 1564.04  5658.6 1569.24  5671.6 1568.07  5765.8 1570.48
#Mann= 11 ,-1 , 0
  4061.5     .07       0  4146.6      .1       0  4463.1     .07       0
    4547      .1       0  4983.6     .05       0    4996      .1       0
  5037.9     .07       0  5113.3      .1       0  5146.6    .035       0
  5578.4     .07       0  5581.4      .1       0
#XS Ineff= 2 , 0
         4553.85 1565.87  5100.5         1560.84
Permanent Ineff=
       F       F
Bank Sta=4983.6,4996
XS Rating Curve= 0 ,0
Exp/Cntr=0.3,0.1

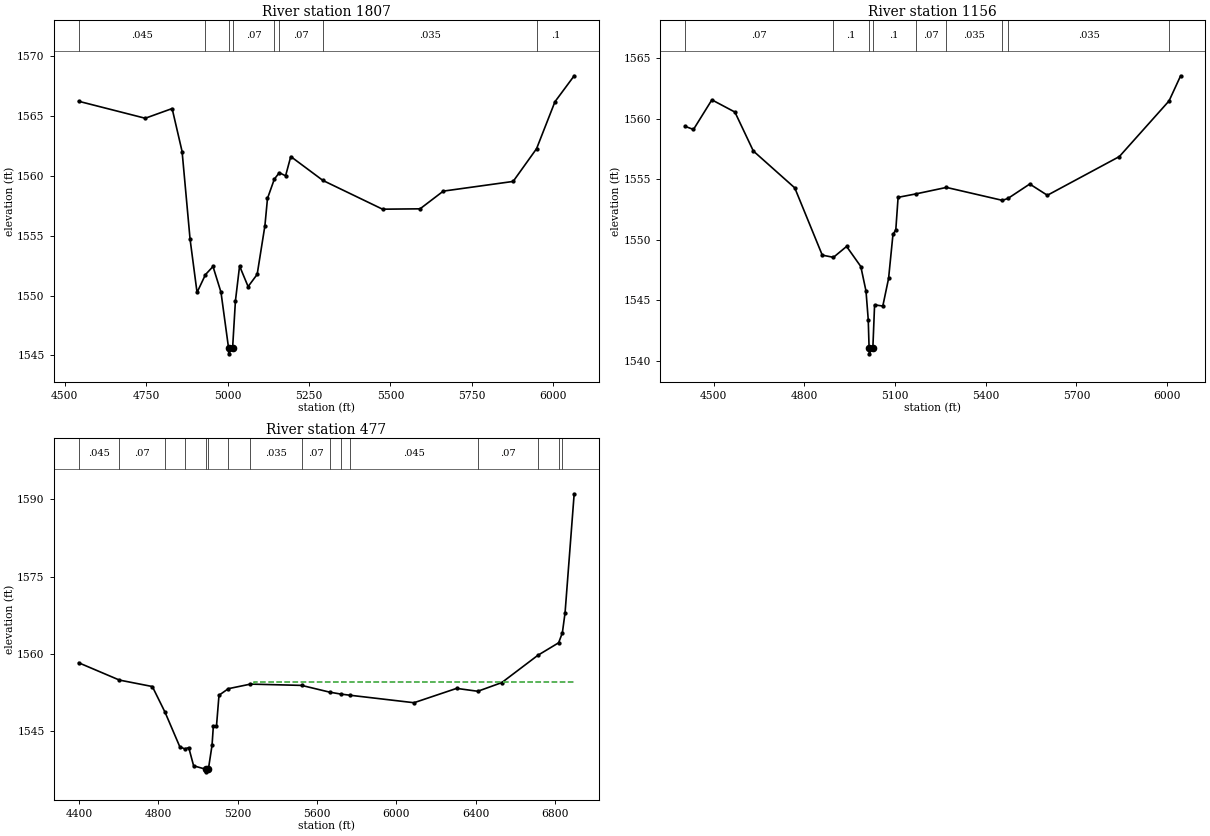
Type RM Length L Ch R = 1 ,1807    ,651,651,651
BEGIN DESCRIPTION:
Spring Creek 2 3.0
END DESCRIPTION:
XS GIS Cut Line= 3
      1949677.97     13878182.33      1950119.64     13878271.14
      1950929.09     13877569.68
#Sta/Elev= 30
  4542.5 1566.24    4747 1564.82  4829.6 1565.63  4860.2 1562.04  4884.7 1554.71
  4906.1 1550.26  4931.9 1551.75  4955.1 1552.43  4979.6 1550.28  5002.8 1545.63
  5003.3 1545.13  5015.3 1545.63  5023.9 1549.54  5036.7 1552.47  5062.9 1550.75
  5090.7 1551.77  5114.5 1555.84  5122.4 1558.12  5143.4 1559.73  5158.6 1560.27
    5178 1560.01  5193.9 1561.62  5292.7 1559.62  5475.7 1557.22  5590.9 1557.25
  5662.3 1558.73  5876.7 1559.54  5948.7 1562.28  6005.1  1566.2  6064.1 1568.37
#Mann= 8 ,-1 , 0
  4542.5    .045       0  4931.9     .07       0  5002.8     .05       0
  5015.3     .07       0  5143.4      .1       0  5158.6     .07       0
  5292.7    .035       0  5948.7      .1       0
#XS Ineff= 2 , 0
                          5198.4         1561.07
Permanent Ineff=
       F       F
Bank Sta=5002.8,5015.3
XS Rating Curve= 0 ,0
Exp/Cntr=0.3,0.1

Type RM Length L Ch R = 1 ,1156    ,679,679,679
BEGIN DESCRIPTION:
Spring Creek 2 2.0
END DESCRIPTION:
XS GIS Cut Line= 4
      1950031.19     13878639.11      1950481.54     13878719.29
      1950638.34     13878559.69       1950915.8     13877642.19
#Sta/Elev= 30
  4405.3 1559.37    4433 1559.11  4493.9 1561.56  4570.1 1560.55  4631.1 1557.33
  4768.2 1554.28  4859.2 1548.72  4896.2 1548.54  4939.7 1549.44  4986.7 1547.78
  5003.9 1545.75  5011.3 1543.39  5014.1 1541.06  5014.6 1540.56  5026.6 1541.06
  5032.3 1544.61  5059.5 1544.51  5078.6 1546.79  5093.1 1550.43  5102.5 1550.81
  5110.1  1553.5  5168.3 1553.78  5270.1 1554.32  5455.2 1553.25  5473.7 1553.41
  5545.7  1554.6    5604 1553.67  5842.2 1556.87  6006.6 1561.47    6045 1563.55
#Mann= 9 ,-1 , 0
  4405.3     .07       0  4896.2      .1       0  5014.1     .05       0
  5026.6      .1       0  5168.3     .07       0  5270.1    .035       0
  5455.2    .045       0  5473.7    .035       0  6006.6      .1       0
#XS Ineff= 2 , 0
                         5267.66         1554.17
Permanent Ineff=
       F       F
Bank Sta=5014.1,5026.6
XS Rating Curve= 0 ,0
Exp/Cntr=0.3,0.1

Type RM Length L Ch R = 1 ,477     ,0,0,0
BEGIN DESCRIPTION:
Spring Creek 2 1.0
END DESCRIPTION:
XS GIS Cut Line= 3
      1950074.95       13879175.        1950675.       13879125.
        1952475.       13878525.
#Sta/Elev= 30
  4397.8 1558.32  4603.6 1554.96  4769.6 1553.71  4833.8 1548.71  4907.7 1542.07
    4933 1541.61  4953.2 1541.87  4977.8 1538.34  5039.3 1537.67  5039.8 1537.17
  5052.2 1537.67  5070.7 1542.31  5077.4  1546.1  5093.2 1546.07  5105.8 1552.02
  5152.9 1553.29  5264.7 1554.18  5522.5 1553.93    5664 1552.62  5721.2 1552.24
    5769 1552.01  6089.3 1550.57  6304.3 1553.35  6411.1 1552.79  6532.1 1554.47
    6714 1559.76  6818.9 1562.19  6837.8 1564.13  6851.4 1568.03  6897.3 1591.08
#Mann= 16 ,-1 , 0
  4397.8    .045       0  4603.6     .07       0  4833.8      .1       0
    4933      .1       0  5039.3     .05       0  5052.2      .1       0
  5152.9     .07       0  5264.7    .035       0  5522.5     .07       0
    5664    .045       0  5721.2    .035       0    5769    .045       0
  6411.1     .07       0    6714      .1       0  6818.9     .07       0
  6837.8      .1       0
#XS Ineff= 2 , 0
                         5281.44         1554.59
Permanent Ineff=
       F       F
Bank Sta=5039.3,5052.2
XS Rating Curve= 0 ,0
Exp/Cntr=0.3,0.1

Chan Stop Cuts=-1
Use User Specified Reach Order=0
Composite Channel Slope=5