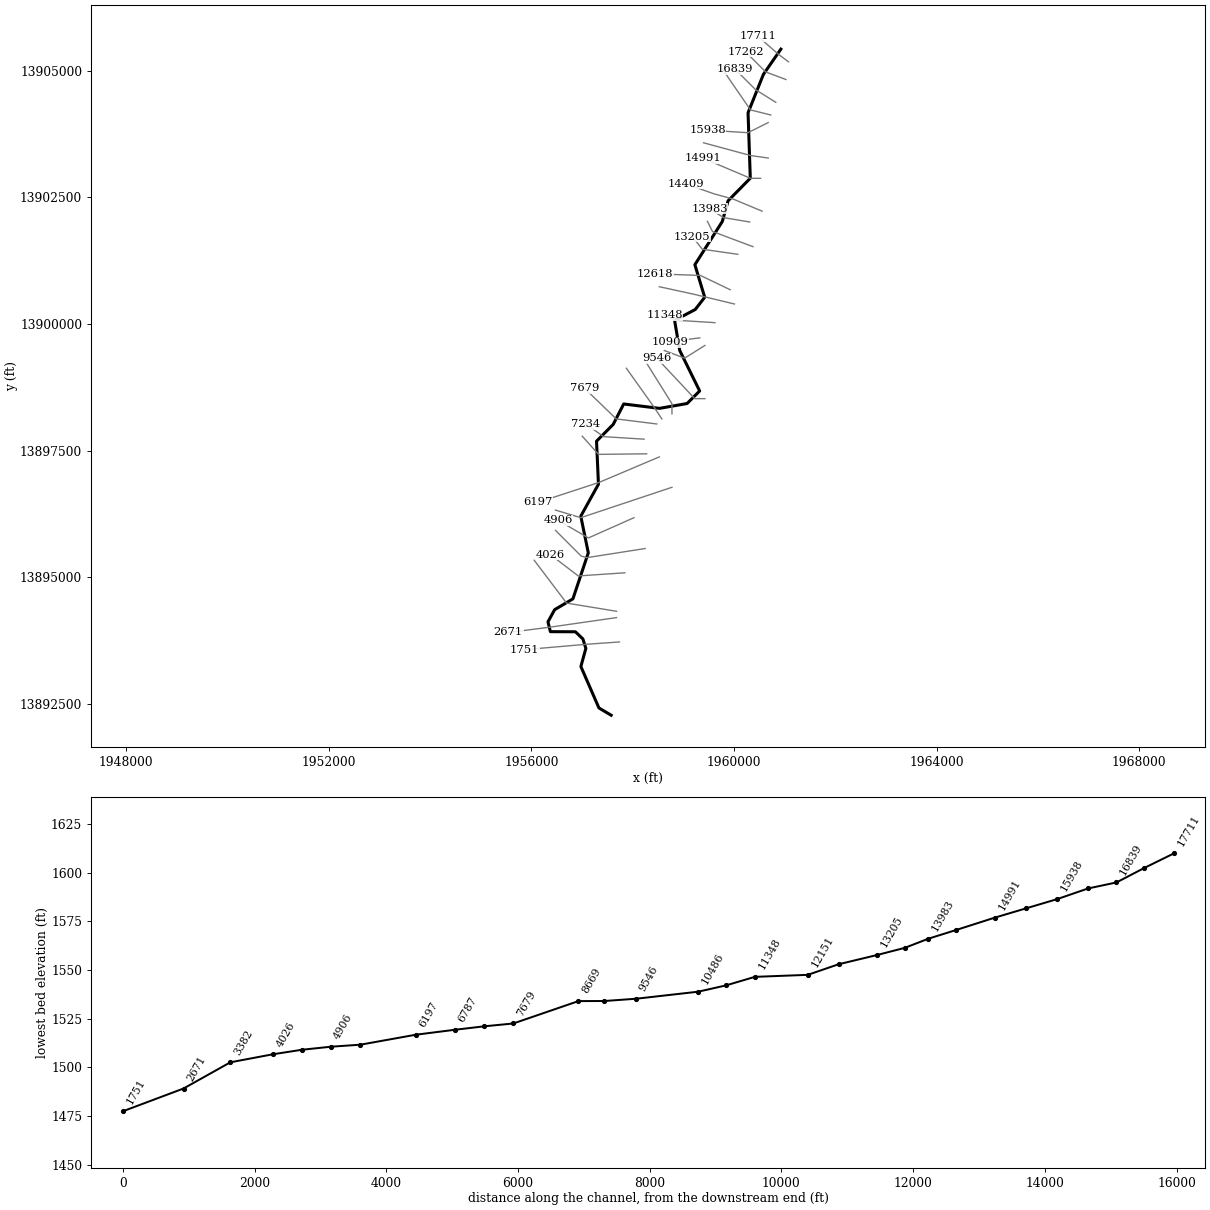
--- Steel Creek.prj (project) ---

Proj Title=Steel Creek Base Level Engineering
Current Plan=p01
Default Exp/Contr=0.3,0.1
English Units
Geom File=g01
Flow File=f01
Plan File=p01
BEGIN DESCRIPTION:
Steel Creek
END DESCRIPTION:

--- Steel Creek.p01 (plan) ---

Plan Title=Multiple Run
Short Identifier=Multiple
Geom File=g01
Flow File=f01
Subcritical Flow
K Sum by GR= 0
Std Step Tol= 0.01
Critical Tol= 0.01
Num of Std Step Trials= 20
Max Error Tol= 0.3
Flow Tol Ratio= 0.001
Split Flow NTrial= 30
Split Flow Tol= 0.02
Split Flow Ratio= 0.02
Log Output Level= 0
Friction Slope Method= 1
Unsteady Friction Slope Method= 2
Unsteady Bridges Friction Slope Method= 1
Parabolic Critical Depth
Global Vel Dist=  1 , 1 , 1
Global Log Level= 0
CheckData=True
Encroach Param= -1, 0, 0, 0
BEGIN DESCRIPTION:
Multiple Run
END DESCRIPTION:

--- Steel Creek.f01 (steady flow) ---

Flow Title=Multiple
Number of Profiles=7
Profile Names=10-year,25-year,50-year,1pct_min,100-year,1pct_plu,500-year
River Rch & RM= Steel Creek,Reach-1,17711
    2483    4444    6404    4455    8889   17736   16921
River Rch & RM= Steel Creek,Reach-1,13983
    4110    7458   10839    7584   15132   30193   29163
River Rch & RM= Steel Creek,Reach-1,7679
    4159    7543   10959    7664   15291   30510   29440
River Rch & RM= Steel Creek,Reach-1,6197
    5294    9682   14141    9934   19821   39548   38509
Boundary for River Rch & Prof#=Steel Creek,Reach-1,1
Up Type=0
Dn Type=3
Dn Slope=0.005
Boundary for River Rch & Prof#=Steel Creek,Reach-1,2
Up Type=0
Dn Type=3
Dn Slope=0.005
Boundary for River Rch & Prof#=Steel Creek,Reach-1,3
Up Type=0
Dn Type=3
Dn Slope=0.005
Boundary for River Rch & Prof#=Steel Creek,Reach-1,4
Up Type=0
Dn Type=3
Dn Slope=0.005
Boundary for River Rch & Prof#=Steel Creek,Reach-1,5
Up Type=0
Dn Type=3
Dn Slope=0.005
Boundary for River Rch & Prof#=Steel Creek,Reach-1,6
Up Type=0
Dn Type=3
Dn Slope=0.005
Boundary for River Rch & Prof#=Steel Creek,Reach-1,7
Up Type=0
Dn Type=3
Dn Slope=0.005

--- Steel Creek.g01 (geometry) ---

Geom Title=Existing Conditions

River Reach=Steel Creek,Reach-1
Reach XY= 30
      1960925.00     13905425.00      1960580.83     13904927.30
      1960277.24     13904169.07      1960321.54     13902876.50
      1959883.12     13902431.07      1959769.18     13902022.69
      1959227.17     13901169.03      1959421.46     13900526.46
      1959235.10     13900285.39      1958826.97     13900069.33
      1958928.14     13899476.64      1959321.69     13898676.73
      1959073.45     13898428.75      1958528.22     13898333.28
      1957822.30     13898419.64      1957614.24     13898015.32
      1957285.97     13897685.38      1957323.85     13896835.48
      1956975.07     13896204.97      1957123.37     13895481.04
      1956819.64     13894572.30      1956458.20     13894358.58
      1956327.16     13894119.03      1956375.00     13893925.00
      1956869.15     13893922.94      1957016.86     13893781.06
      1957075.20     13893595.05      1956976.80     13893237.00
      1957333.14     13892418.94      1957575.00     13892275.00

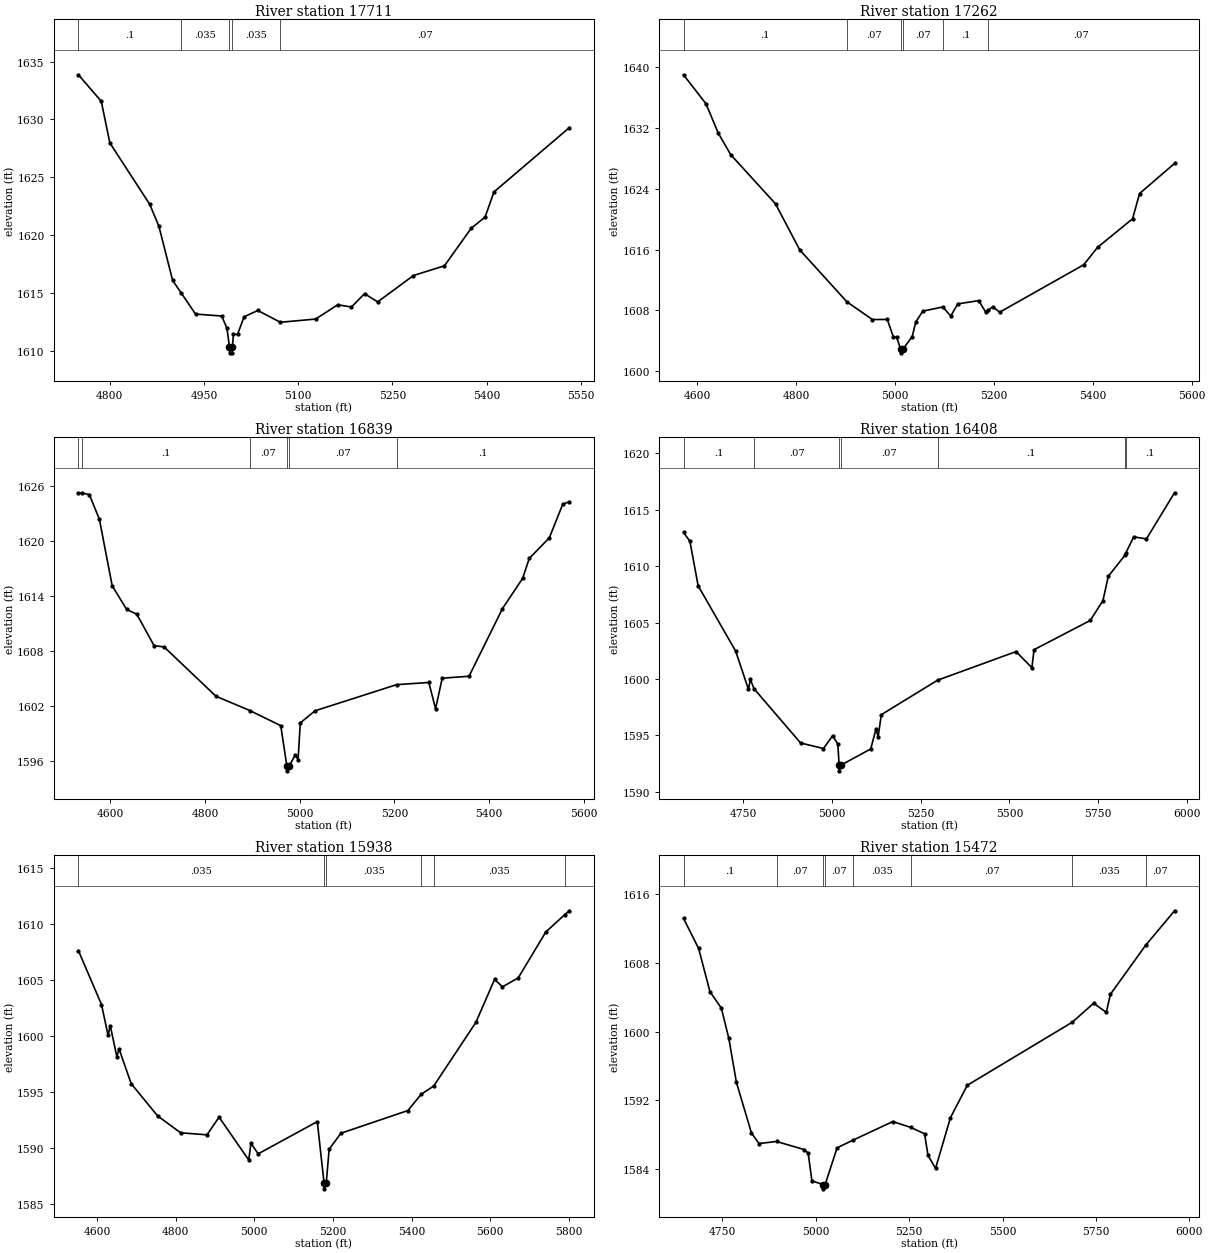
Type RM Length L Ch R = 1,17711,449,449,449
BEGIN DESCRIPTION:
Steel Creek 31.0
END DESCRIPTION:
XS GIS Cut Line= 3
      1961074.96     13905175.03      1960875.00     13905325.00
      1960474.97     13905675.03
#Sta/Elev= 30
  4750.2 1633.86  4786.6 1631.57  4800.2 1627.98  4863.7 1622.67  4878.3 1620.78
  4900.2 1616.09  4914.0 1615.00  4936.6 1613.19  4978.3 1613.02  4986.6 1611.97
  4990.6 1610.34  4990.9 1609.84  4994.9 1609.84  4995.2 1610.34  4997.0 1611.44
  5003.5 1611.44  5013.9 1612.95  5035.7 1613.50  5071.6 1612.48  5127.8 1612.76
  5162.9 1613.99  5184.8 1613.80  5205.6 1614.95  5226.5 1614.24  5283.5 1616.52
  5332.8 1617.36  5375.5 1620.61  5397.4 1621.56  5411.6 1623.74  5531.7 1629.30
#Mann=5,-1,0
  4750.2     0.1       0  4914.0   0.035       0  4990.6   0.035       0
  4995.2   0.035       0  5071.6    0.07       0
Bank Sta=4990.6,4995.2
Exp/Cntr=0.3,0.1

Type RM Length L Ch R = 1,17262,423,423,423
BEGIN DESCRIPTION:
Steel Creek 30.0
END DESCRIPTION:
XS GIS Cut Line= 3
      1961024.96     13904825.01      1960625.00     13904975.00
      1960225.03     13905374.97
#Sta/Elev= 30
  4572.6 1639.03  4618.0 1635.21  4642.9 1631.34  4667.8 1628.52  4758.6 1622.02
  4807.5 1615.96  4902.9 1609.11  4954.4 1606.77  4984.6 1606.78  4997.1 1604.45
  5003.3 1604.45  5011.6 1602.88  5011.9 1602.38  5016.3 1602.88  5035.1 1604.52
  5042.2 1606.44  5056.3 1607.87  5097.0 1608.43  5112.9 1607.22  5127.0 1608.83
  5169.5 1609.26  5183.6 1607.75  5188.6 1608.00  5197.8 1608.45  5211.9 1607.74
  5381.6 1613.98  5409.9 1616.29  5480.6 1620.05  5494.7 1623.38  5565.4 1627.34
#Mann=6,-1,0
  4572.6     0.1       0  4902.9    0.07       0  5011.6    0.05       0
  5016.3    0.07       0  5097.0     0.1       0  5188.6    0.07       0
Bank Sta=5011.6,5016.3
Exp/Cntr=0.3,0.1

Type RM Length L Ch R = 1,16839,431,431,431
BEGIN DESCRIPTION:
Steel Creek 29.0
END DESCRIPTION:
XS GIS Cut Line= 3
      1960825.03     13904374.98      1960425.00     13904625.00
      1960025.02     13905024.98
#Sta/Elev= 30
  4532.2 1625.21  4539.7 1625.18  4555.2 1625.02  4576.5 1622.33  4603.6 1615.08
  4634.2 1612.50  4655.5 1611.99  4692.0 1608.57  4713.3 1608.42  4822.9 1603.05
  4894.3 1601.50  4959.7 1599.85  4972.7 1595.43  4973.0 1594.93  4977.4 1595.43
  4990.4 1596.67  4996.3 1596.14  5001.0 1600.15  5032.2 1601.47  5204.8 1604.32
  5272.6 1604.55  5286.8 1601.69  5300.9 1605.02  5357.5 1605.23  5428.2 1612.60
  5470.6 1615.88  5484.8 1618.06  5527.2 1620.31  5555.5 1623.96  5569.6 1624.24
#Mann=6,-1,0
  4532.2    0.07       0  4539.7     0.1       0  4894.3    0.07       0
  4972.7    0.05       0  4977.4    0.07       0  5204.8     0.1       0
Bank Sta=4972.7,4977.4
Exp/Cntr=0.3,0.1

Type RM Length L Ch R = 1,16408,470,470,470
BEGIN DESCRIPTION:
Steel Creek 28.0
END DESCRIPTION:
XS GIS Cut Line= 3
      1960725.00     13904125.00      1960325.00     13904225.00
      1959775.02     13905024.98
#Sta/Elev= 30
  4582.0 1612.99  4600.0 1612.21  4623.2 1608.26  4728.9 1602.46  4765.0 1599.06
  4770.1 1599.97  4780.5 1599.13  4911.8 1594.31  4976.3 1593.82  5001.8 1594.95
  5016.6 1594.22  5020.4 1592.34  5020.7 1591.84  5025.1 1592.34  5109.3 1593.78
  5124.2 1595.54  5130.3 1594.87  5139.1 1596.82  5297.5 1599.88  5518.6 1602.42
  5563.3 1600.99  5569.4 1602.59  5727.7 1605.18  5763.5 1606.95  5778.4 1609.09
  5825.3 1610.97  5827.7 1611.16  5850.1 1612.60  5886.0 1612.42  5965.1 1616.51
#Mann=7,-1,0
  4582.0     0.1       0  4780.5    0.07       0  5020.4    0.05       0
  5025.1    0.07       0  5297.5     0.1       0  5825.3    0.07       0
  5827.7     0.1       0
Bank Sta=5020.4,5025.1
Exp/Cntr=0.3,0.1

Type RM Length L Ch R = 1,15938,466,466,466
BEGIN DESCRIPTION:
Steel Creek 27.0
END DESCRIPTION:
XS GIS Cut Line= 3
      1960674.98     13903974.99      1960275.00     13903775.00
      1959475.05     13903825.00
#Sta/Elev= 30
  4552.8 1607.66  4611.5 1602.84  4628.2 1600.10  4633.8 1600.95  4650.6 1598.17
  4656.2 1598.87  4686.9 1595.77  4754.0 1592.89  4812.7 1591.37  4879.8 1591.19
  4910.5 1592.77  4986.0 1588.94  4991.6 1590.44  5010.0 1589.49  5160.3 1592.37
  5177.6 1586.86  5178.0 1586.36  5183.1 1586.86  5190.4 1589.90  5220.4 1591.33
  5390.7 1593.36  5424.7 1594.82  5456.3 1595.55  5563.6 1601.24  5611.2 1605.09
  5631.2 1604.42  5671.3 1605.22  5741.4 1609.32  5789.7 1610.88  5801.5 1611.22
#Mann=6,-1,0
  4552.8   0.035       0  5177.6   0.035       0  5183.1   0.035       0
  5424.7     0.1       0  5456.3   0.035       0  5789.7    0.07       0
Bank Sta=5177.6,5183.1
Exp/Cntr=0.3,0.1

Type RM Length L Ch R = 1,15472,481,481,481
BEGIN DESCRIPTION:
Steel Creek 26.0
END DESCRIPTION:
XS GIS Cut Line= 3
      1960674.96     13903275.01      1960325.00     13903325.00
      1959398.81     13903575.96
#Sta/Elev= 30
  4646.9 1613.20  4687.3 1609.70  4717.6 1604.66  4747.9 1602.76  4768.1 1599.22
  4788.3 1594.10  4828.7 1588.17  4848.9 1586.96  4895.7 1587.20  4970.1 1586.25
  4980.2 1585.84  4990.3 1582.61  5020.2 1582.18  5020.6 1581.68  5025.7 1582.18
  5057.6 1586.46  5100.9 1587.37  5206.6 1589.52  5254.5 1588.84  5291.4 1588.10
  5300.9 1585.57  5320.9 1584.06  5360.8 1589.98  5405.8 1593.75  5686.5 1601.10
  5743.6 1603.31  5777.5 1602.25  5788.6 1604.36  5882.4 1610.05  5960.0 1614.09
#Mann=8,-1,0
  4646.9     0.1       0  4895.7    0.07       0  5020.2    0.05       0
  5025.7    0.07       0  5100.9   0.035       0  5254.5    0.07       0
  5686.5   0.035       0  5882.4    0.07       0
Bank Sta=5020.2,5025.7
Exp/Cntr=0.3,0.1

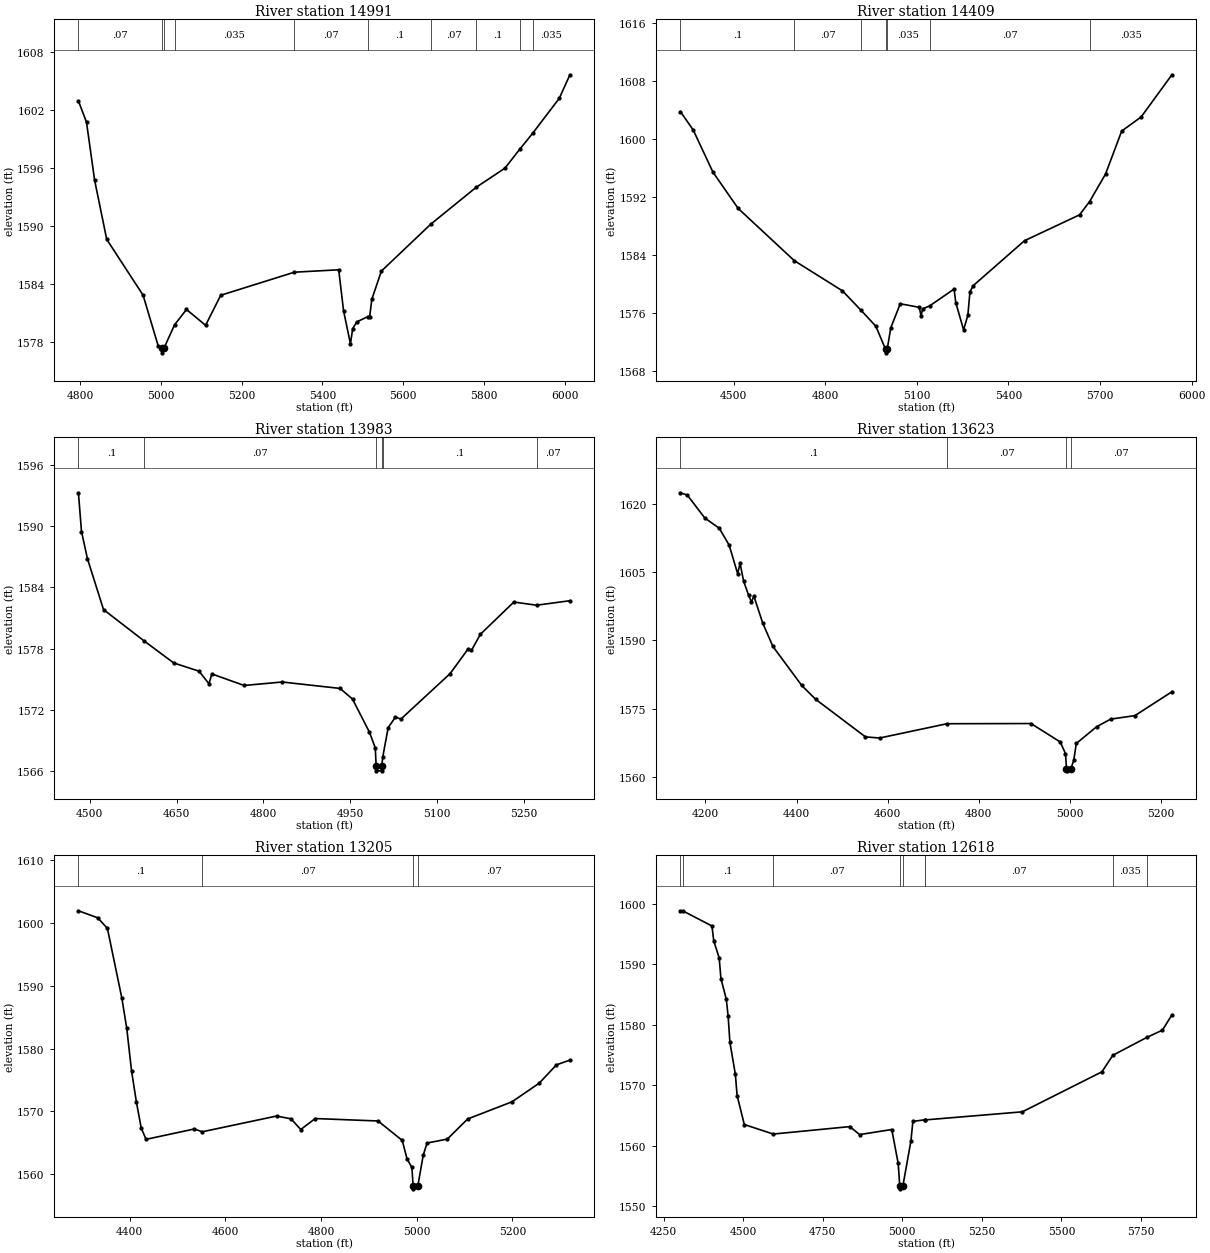
Type RM Length L Ch R = 1,14991,582,582,582
BEGIN DESCRIPTION:
Steel Creek 25.0
END DESCRIPTION:
XS GIS Cut Line= 3
      1960525.03     13902875.00      1960325.00     13902875.00
      1959389.35     13903271.69
#Sta/Elev= 30
  4796.2 1602.93  4816.2 1600.73  4836.2 1594.74  4866.2 1588.60  4956.2 1582.82
  4993.7 1577.56  5002.6 1577.35  5003.0 1576.85  5008.1 1577.35  5034.1 1579.75
  5063.6 1581.34  5110.9 1579.70  5148.3 1582.81  5330.6 1585.20  5440.3 1585.45
  5452.4 1581.19  5469.4 1577.78  5474.9 1579.35  5485.0 1580.05  5512.7 1580.61
  5516.8 1580.53  5522.2 1582.38  5545.9 1585.31  5668.4 1590.18  5780.6 1593.99
  5851.7 1595.97  5889.1 1597.97  5920.3 1599.58  5986.3 1603.21  6012.5 1605.64
#Mann=10,-1,0
  4796.2    0.07       0  5002.6    0.05       0  5008.1    0.07       0
  5034.1   0.035       0  5330.6    0.07       0  5512.7     0.1       0
  5668.4    0.07       0  5780.6     0.1       0  5889.1    0.07       0
  5920.3   0.035       0
Bank Sta=5002.6,5008.1
Exp/Cntr=0.3,0.1

Type RM Length L Ch R = 1,14409,426,426,426
BEGIN DESCRIPTION:
Steel Creek 24.1
END DESCRIPTION:
XS GIS Cut Line= 4
      1960553.62     13902226.86      1959988.18     13902463.40
      1959597.57     13902570.76      1959040.06     13902768.35
#Sta/Elev= 30
  4325.8 1603.84  4367.7 1601.30  4432.4 1595.48  4514.7 1590.49  4698.6 1583.28
  4856.5 1579.11  4917.7 1576.41  4965.8 1574.23  4997.4 1571.06  4997.8 1570.56
  5003.0 1571.06  5014.6 1574.00  5045.7 1577.33  5107.9 1576.84  5113.8 1575.65
  5119.0 1576.63  5141.8 1577.03  5222.0 1579.36  5227.5 1577.50  5253.1 1573.73
  5267.1 1575.75  5273.9 1578.95  5284.3 1579.82  5452.6 1586.03  5633.0 1589.60
  5665.8 1591.43  5717.9 1595.22  5770.9 1601.16  5834.6 1603.10  5935.3 1608.92
#Mann=7,-1,0
  4325.8     0.1       0  4698.6    0.07       0  4917.7   0.035       0
  4997.4   0.035       0  5003.0   0.035       0  5141.8    0.07       0
  5665.8   0.035       0
Bank Sta=4997.4,5003
Exp/Cntr=0.3,0.1

Type RM Length L Ch R = 1,13983,360,360,360
BEGIN DESCRIPTION:
Steel Creek 24.0
END DESCRIPTION:
XS GIS Cut Line= 3
      1960310.25     13902012.43      1959797.48     13902098.40
      1959518.42     13902271.28
#Sta/Elev= 30
  4480.7 1593.27  4486.0 1589.47  4496.2 1586.83  4524.0 1581.83  4594.6 1578.74
  4645.3 1576.60  4688.8 1575.80  4706.0 1574.57  4711.0 1575.53  4766.6 1574.40
  4832.4 1574.74  4932.2 1574.11  4953.7 1573.07  4982.9 1569.83  4993.0 1568.29
  4994.5 1566.54  4995.0 1566.04  5003.8 1566.04  5004.3 1566.54  5005.8 1567.36
  5015.3 1570.28  5027.8 1571.30  5037.3 1571.11  5122.3 1575.57  5153.1 1577.97
  5159.0 1577.83  5174.3 1579.41  5232.2 1582.57  5271.4 1582.26  5328.9 1582.70
#Mann=6,-1,0
  4480.7     0.1       0  4594.6    0.07       0  4994.5    0.05       0
  5004.3    0.07       0  5005.8     0.1       0  5271.4    0.07       0
Bank Sta=4994.5,5004.3
Exp/Cntr=0.3,0.1

Type RM Length L Ch R = 1,13623,418,418,418
BEGIN DESCRIPTION:
Steel Creek 23.0
END DESCRIPTION:
XS GIS Cut Line= 3
      1960374.97     13901525.01      1959575.00     13901825.00
      1959474.99     13902025.02
#Sta/Elev= 30
  4145.4 1622.40  4160.5 1621.89  4198.8 1616.87  4230.8 1614.59  4252.2 1610.91
  4270.9 1604.64  4276.2 1606.88  4284.2 1602.92  4294.9 1599.92  4301.1 1598.41
  4306.5 1599.70  4326.0 1593.75  4348.3 1588.64  4411.5 1580.07  4441.7 1577.06
  4551.2 1568.78  4582.4 1568.53  4730.1 1571.67  4914.3 1571.71  4978.4 1567.67
  4990.0 1565.10  4992.2 1561.82  4992.7 1561.32  5002.0 1561.82  5008.2 1563.67
  5013.7 1567.33  5058.5 1571.03  5089.2 1572.68  5142.3 1573.45  5223.4 1578.69
#Mann=4,-1,0
  4145.4     0.1       0  4730.1    0.07       0  4992.2    0.05       0
  5002.0    0.07       0
Bank Sta=4992.2,5002
Exp/Cntr=0.3,0.1

Type RM Length L Ch R = 1,13205,587,587,587
BEGIN DESCRIPTION:
Steel Creek 22.0
END DESCRIPTION:
XS GIS Cut Line= 3
      1960074.99     13901375.00      1959375.00     13901475.00
      1959174.97     13901725.03
#Sta/Elev= 30
  4292.9 1601.93  4333.3 1600.81  4353.5 1599.12  4383.8 1587.97  4393.9 1583.22
  4404.0 1576.41  4414.1 1571.47  4424.2 1567.33  4434.3 1565.55  4535.3 1567.20
  4551.7 1566.75  4707.1 1569.26  4737.4 1568.81  4757.6 1567.11  4787.9 1568.86
  4919.2 1568.47  4969.7 1565.38  4979.8 1562.43  4989.9 1561.07  4992.5 1558.17
  4993.0 1557.67  5002.4 1558.17  5013.6 1563.02  5021.6 1564.96  5064.0 1565.59
  5106.5 1568.79  5199.3 1571.53  5256.1 1574.49  5292.1 1577.41  5320.2 1578.16
#Mann=4,-1,0
  4292.9     0.1       0  4551.7    0.07       0  4992.5    0.05       0
  5002.4    0.07       0
Bank Sta=4992.5,5002.4
Exp/Cntr=0.3,0.1

Type RM Length L Ch R = 1,12618,467,467,467
BEGIN DESCRIPTION:
Steel Creek 21.0
END DESCRIPTION:
XS GIS Cut Line= 3
      1959925.02     13900674.99      1959337.43     13900957.12
      1958445.22     13900989.26
#Sta/Elev= 30
  4302.5 1598.83  4310.8 1598.79  4401.6 1596.32  4407.2 1593.87  4424.3 1591.04
  4429.8 1587.63  4446.7 1584.22  4452.5 1581.37  4458.0 1577.10  4475.1 1571.83
  4480.7 1568.29  4503.3 1563.52  4594.3 1561.95  4835.0 1563.18  4865.6 1561.86
  4966.7 1562.70  4986.8 1557.11  4991.8 1553.40  4992.3 1552.90  5001.7 1553.40
  5026.8 1560.78  5033.1 1564.04  5069.9 1564.30  5072.7 1564.29  5377.0 1565.62
  5627.2 1572.23  5661.4 1574.96  5768.1 1577.91  5817.3 1579.11  5847.1 1581.63
#Mann=9,-1,0
  4302.5    0.07       0  4310.8     0.1       0  4594.3    0.07       0
  4991.8    0.05       0  5001.7    0.07       0  5069.9     0.1       0
  5072.7    0.07       0  5661.4   0.035       0  5768.1    0.07       0
Bank Sta=4991.8,5001.7
Exp/Cntr=0.3,0.1

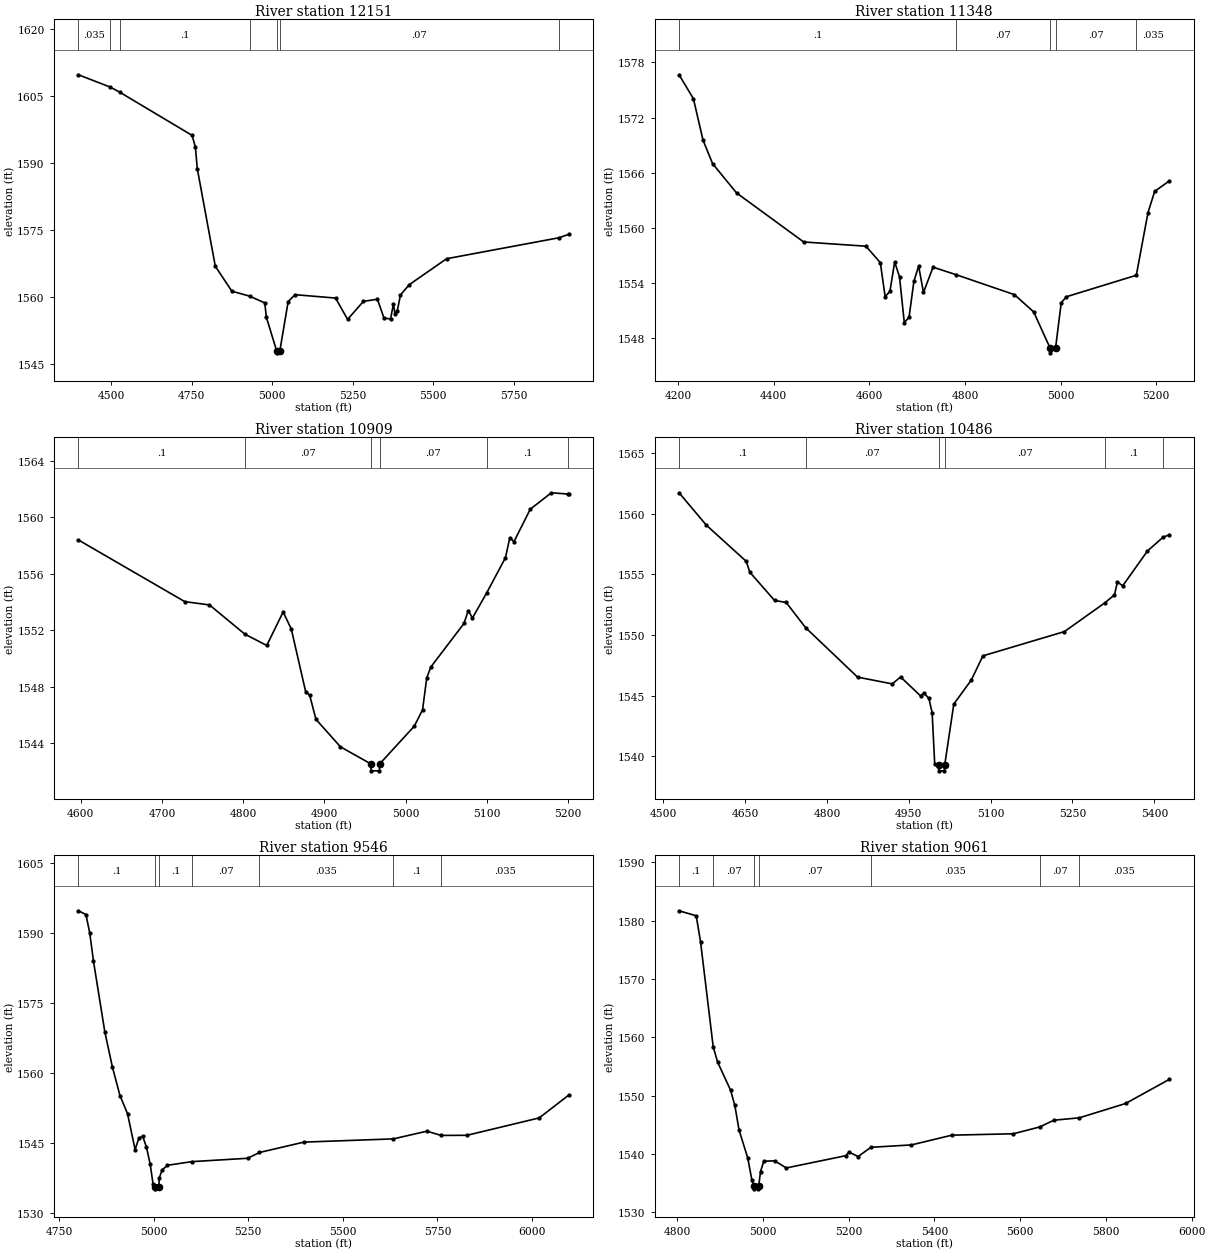
Type RM Length L Ch R = 1,12151,803,803,803
BEGIN DESCRIPTION:
Steel Creek 20.1
END DESCRIPTION:
XS GIS Cut Line= 3
      1960008.47     13900393.40      1959203.96     13900587.19
      1958524.52     13900734.77
#Sta/Elev= 30
  4398.5 1609.81  4496.9 1607.07  4526.4 1605.93  4751.8 1596.22  4762.1 1593.53
  4767.8 1588.78  4823.8 1566.88  4875.2 1561.29  4930.4 1560.18  4977.4 1558.66
  4982.5 1555.43  5014.1 1547.97  5014.6 1547.47  5024.4 1547.97  5050.1 1558.96
  5071.5 1560.51  5197.3 1559.75  5234.7 1554.97  5283.8 1559.01  5327.3 1559.49
  5347.8 1555.24  5368.2 1555.08  5377.0 1558.40  5382.1 1556.20  5388.7 1556.77
  5398.9 1560.44  5426.1 1562.75  5542.2 1568.57  5891.2 1573.27  5921.3 1574.03
#Mann=7,-1,0
  4398.5   0.035       0  4496.9    0.07       0  4526.4     0.1       0
  4930.4    0.07       0  5014.1    0.05       0  5024.4    0.07       0
  5891.2   0.035       0
Bank Sta=5014.1,5024.4
Exp/Cntr=0.3,0.1

Type RM Length L Ch R = 1,11348,439,439,439
BEGIN DESCRIPTION:
Steel Creek 20.0
END DESCRIPTION:
XS GIS Cut Line= 3
      1959624.97     13900025.00      1958825.00     13900075.00
      1958625.03     13900174.98
#Sta/Elev= 30
  4202.4 1576.66  4232.4 1574.06  4252.5 1569.55  4272.5 1567.00  4322.6 1563.82
  4462.9 1558.49  4593.1 1558.03  4623.2 1556.24  4633.2 1552.55  4643.2 1553.11
  4653.2 1556.32  4663.3 1554.70  4673.3 1549.72  4683.3 1550.32  4693.3 1554.20
  4703.3 1555.87  4713.4 1553.00  4733.4 1555.75  4781.8 1554.93  4903.7 1552.76
  4943.8 1550.89  4978.3 1546.94  4978.8 1546.44  4989.5 1546.94  5001.4 1551.88
  5012.3 1552.54  5158.4 1554.87  5182.8 1561.68  5196.8 1563.99  5227.5 1565.13
#Mann=5,-1,0
  4202.4     0.1       0  4781.8    0.07       0  4978.3    0.05       0
  4989.5    0.07       0  5158.4   0.035       0
Bank Sta=4978.3,4989.5
Exp/Cntr=0.3,0.1

Type RM Length L Ch R = 1,10909,423,423,423
BEGIN DESCRIPTION:
Steel Creek 19.0
END DESCRIPTION:
XS GIS Cut Line= 3
      1959325.01     13899725.00      1958925.00     13899675.00
      1958728.67     13899635.93
#Sta/Elev= 30
  4597.2 1558.40  4728.2 1554.03  4758.5 1553.80  4802.0 1551.73  4829.0 1550.93
  4849.2 1553.30  4859.2 1552.09  4876.9 1547.65  4881.9 1547.39  4889.5 1545.70
  4919.7 1543.75  4956.9 1542.55  4957.4 1542.05  4967.6 1542.05  4968.1 1542.55
  5010.5 1545.21  5020.7 1546.37  5025.9 1548.64  5031.0 1549.41  5071.7 1552.49
  5077.0 1553.40  5082.1 1552.87  5099.7 1554.66  5122.7 1557.14  5128.1 1558.56
  5133.2 1558.28  5153.3 1560.58  5179.2 1561.74  5199.6 1561.65  5200.5 1561.64
#Mann=6,-1,0
  4597.2     0.1       0  4802.0    0.07       0  4956.9    0.05       0
  4968.1    0.07       0  5099.7     0.1       0  5199.6   0.035       0
Bank Sta=4956.9,4968.1
Exp/Cntr=0.3,0.1

Type RM Length L Ch R = 1,10486,940,940,940
BEGIN DESCRIPTION:
Steel Creek 18.0
END DESCRIPTION:
XS GIS Cut Line= 3
      1959424.98     13899574.99      1959025.00     13899325.00
      1958624.98     13899475.01
#Sta/Elev= 30
  4528.7 1561.71  4578.8 1559.04  4651.9 1556.06  4658.4 1555.17  4703.8 1552.84
  4725.0 1552.68  4760.7 1550.60  4855.9 1546.53  4919.6 1545.97  4934.9 1546.54
  4971.5 1544.98  4977.4 1545.23  4986.8 1544.77  4992.7 1543.58  4997.4 1539.35
  5004.5 1539.31  5005.0 1538.81  5015.3 1538.81  5015.8 1539.31  5032.4 1544.31
  5064.5 1546.29  5085.8 1548.28  5235.3 1550.28  5309.1 1552.64  5327.0 1553.30
  5332.3 1554.36  5342.1 1554.05  5387.5 1556.92  5415.6 1558.03  5427.6 1558.26
#Mann=6,-1,0
  4528.7     0.1       0  4760.7    0.07       0  5004.5    0.05       0
  5015.8    0.07       0  5309.1     0.1       0  5415.6    0.07       0
Bank Sta=5004.5,5015.8
Exp/Cntr=0.3,0.1

Type RM Length L Ch R = 1,9546,485,485,485
BEGIN DESCRIPTION:
Steel Creek 17.0
END DESCRIPTION:
XS GIS Cut Line= 3
      1959425.04     13898525.00      1959225.00     13898525.00
      1958475.02     13899324.98
#Sta/Elev= 30
  4800.6 1594.72  4820.6 1593.92  4830.6 1590.01  4840.6 1583.91  4870.6 1568.78
  4890.6 1561.28  4910.6 1555.17  4930.6 1551.29  4950.6 1543.62  4960.6 1546.04
  4970.6 1546.50  4980.6 1544.12  4990.6 1540.44  4998.1 1536.25  5002.0 1535.71
  5002.5 1535.21  5013.5 1535.71  5014.6 1537.54  5021.9 1539.22  5036.1 1540.25
  5100.5 1541.03  5248.1 1541.75  5279.6 1542.99  5397.0 1545.21  5633.3 1545.90
  5722.3 1547.55  5760.0 1546.64  5828.3 1546.67  6019.3 1550.39  6097.2 1555.26
#Mann=7,-1,0
  4800.6     0.1       0  5002.0    0.05       0  5013.5     0.1       0
  5100.5    0.07       0  5279.6   0.035       0  5633.3     0.1       0
  5760.0   0.035       0
Bank Sta=5002,5013.5
Exp/Cntr=0.3,0.1

Type RM Length L Ch R = 1,9061,392,392,392
BEGIN DESCRIPTION:
Steel Creek 16.0
END DESCRIPTION:
XS GIS Cut Line= 3
      1958775.00     13898225.03      1958775.00     13898425.00
      1958274.98     13899225.03
#Sta/Elev= 30
  4804.6 1581.69  4844.6 1580.83  4854.6 1576.42  4884.2 1558.38  4894.6 1555.73
  4924.6 1550.96  4934.6 1548.33  4944.6 1544.07  4964.6 1539.37  4974.6 1535.46
  4978.8 1534.53  4979.3 1534.03  4989.8 1534.03  4990.3 1534.53  4994.6 1537.00
  5002.1 1538.77  5027.6 1538.83  5054.7 1537.61  5193.2 1539.71  5200.9 1540.32
  5222.1 1539.57  5252.1 1541.15  5346.6 1541.56  5440.9 1543.23  5584.2 1543.47
  5645.8 1544.64  5678.5 1545.79  5737.9 1546.20  5846.0 1548.66  5948.0 1552.80
#Mann=7,-1,0
  4804.6     0.1       0  4884.2    0.07       0  4978.8    0.05       0
  4990.3    0.07       0  5252.1   0.035       0  5645.8    0.07       0
  5737.9   0.035       0
Bank Sta=4978.8,4990.3
Exp/Cntr=0.3,0.1

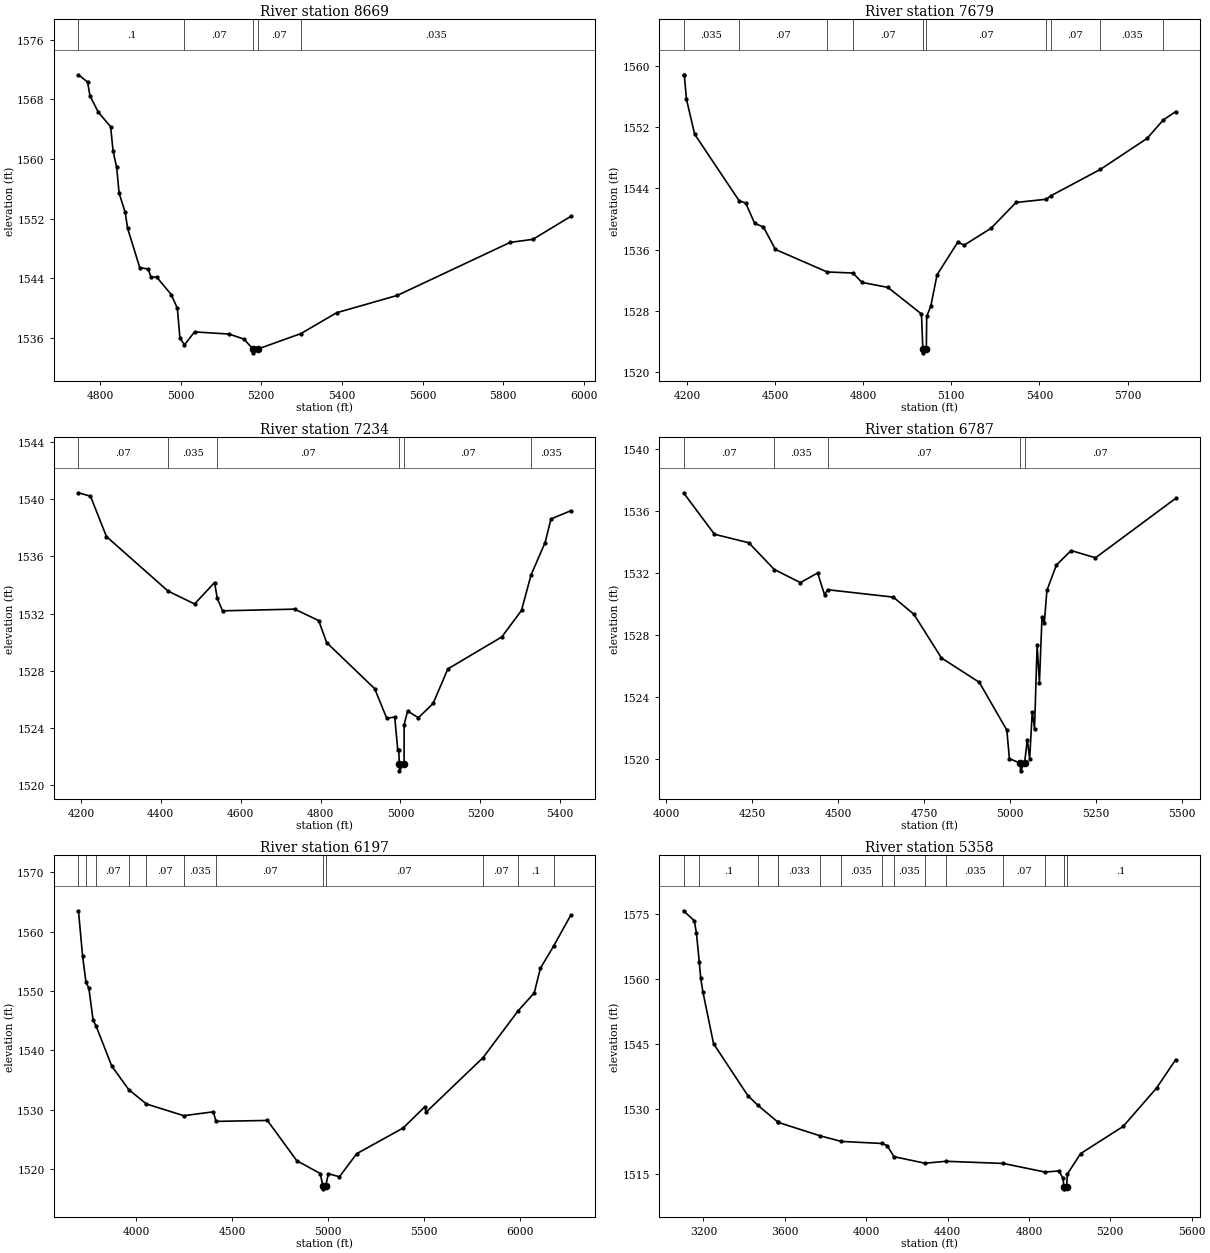
Type RM Length L Ch R = 1,8669,990,990,990
BEGIN DESCRIPTION:
Steel Creek 15.0
END DESCRIPTION:
XS GIS Cut Line= 3
      1958575.00     13898125.00      1958421.45     13898357.31
      1957874.99     13899125.02
#Sta/Elev= 30
  4746.6 1571.30  4769.2 1570.33  4775.2 1568.46  4796.2 1566.25  4826.4 1564.33
  4832.4 1561.09  4841.4 1558.87  4847.4 1555.42  4862.5 1552.84  4868.5 1550.71
  4898.6 1545.43  4919.6 1545.23  4926.4 1544.16  4940.7 1544.15  4976.8 1541.80
  4991.9 1539.97  4998.3 1535.98  5009.6 1535.06  5034.5 1536.80  5120.4 1536.51
  5157.2 1535.83  5179.6 1534.49  5180.1 1533.99  5191.1 1534.49  5298.6 1536.58
  5387.0 1539.37  5537.8 1541.70  5817.4 1548.81  5873.9 1549.22  5967.4 1552.29
#Mann=5,-1,0
  4746.6     0.1       0  5009.6    0.07       0  5179.6    0.05       0
  5191.1    0.07       0  5298.6   0.035       0
Bank Sta=5179.6,5191.1
Exp/Cntr=0.3,0.1

Type RM Length L Ch R = 1,7679,445,445,445
BEGIN DESCRIPTION:
Steel Creek 14.0
END DESCRIPTION:
XS GIS Cut Line= 3
      1958475.00     13898025.00      1957675.00     13898125.00
      1957050.41     13898728.44
#Sta/Elev= 30
  4188.8 1558.86  4191.3 1558.86  4198.9 1555.64  4226.6 1551.09  4378.2 1542.37
  4400.4 1542.08  4430.7 1539.44  4460.9 1538.94  4501.2 1536.02  4677.4 1533.07
  4765.3 1532.93  4796.0 1531.70  4884.2 1531.05  4998.5 1527.57  5003.1 1522.99
  5003.6 1522.49  5015.0 1522.99  5016.3 1527.25  5030.4 1528.64  5051.5 1532.70
  5122.2 1536.98  5143.6 1536.57  5235.4 1538.79  5320.3 1542.16  5423.5 1542.58
  5437.7 1543.01  5607.0 1546.48  5765.9 1550.53  5821.6 1552.96  5863.5 1554.04
#Mann=10,-1,0
  4188.8   0.035       0  4378.2    0.07       0  4677.4   0.035       0
  4765.3    0.07       0  5003.1    0.05       0  5015.0    0.07       0
  5423.5   0.035       0  5437.7    0.07       0  5607.0   0.035       0
  5821.6    0.07       0
Bank Sta=5003.1,5015
Exp/Cntr=0.3,0.1

Type RM Length L Ch R = 1,7234,447,447,447
BEGIN DESCRIPTION:
Steel Creek 13.0
END DESCRIPTION:
XS GIS Cut Line= 3
      1958224.99     13897725.00      1957425.00     13897775.00
      1957074.97     13898025.02
#Sta/Elev= 30
  4194.1 1540.45  4224.2 1540.21  4264.2 1537.39  4418.4 1533.58  4484.7 1532.68
  4534.8 1534.18  4541.4 1533.08  4554.8 1532.20  4735.1 1532.32  4795.3 1531.52
  4815.3 1529.98  4935.5 1526.76  4965.6 1524.69  4985.6 1524.78  4993.1 1522.51
  4995.7 1522.51  4997.0 1521.52  4997.5 1521.02  5009.1 1521.52  5009.2 1524.25
  5017.8 1525.20  5044.8 1524.73  5081.7 1525.73  5118.5 1528.14  5253.7 1530.38
  5302.9 1532.23  5326.8 1534.71  5361.9 1536.97  5376.6 1538.62  5425.8 1539.19
#Mann=6,-1,0
  4194.1    0.07       0  4418.4   0.035       0  4541.4    0.07       0
  4997.0    0.05       0  5009.1    0.07       0  5326.8   0.035       0
Bank Sta=4997,5009.1
Exp/Cntr=0.3,0.1

Type RM Length L Ch R = 1,6787,590,590,590
BEGIN DESCRIPTION:
Steel Creek 12.0
END DESCRIPTION:
XS GIS Cut Line= 3
      1958274.99     13897436.00      1957325.00     13897425.00
      1957004.30     13897783.55
#Sta/Elev= 30
  4049.9 1537.20  4139.9 1534.52  4239.9 1533.97  4314.0 1532.24  4389.9 1531.40
  4439.9 1532.02  4459.9 1530.61  4468.7 1530.94  4659.9 1530.46  4719.9 1529.35
  4799.9 1526.53  4909.9 1524.96  4990.0 1521.87  4997.5 1520.02  5029.4 1519.74
  5029.9 1519.24  5041.5 1519.74  5049.7 1521.26  5056.4 1520.00  5063.9 1523.06
  5070.6 1521.97  5078.1 1527.39  5084.8 1524.93  5092.3 1529.19  5099.0 1528.78
  5106.5 1530.89  5134.1 1532.53  5176.8 1533.47  5247.8 1533.00  5481.0 1536.84
#Mann=5,-1,0
  4049.9    0.07       0  4314.0   0.035       0  4468.7    0.07       0
  5029.4    0.05       0  5041.5    0.07       0
Bank Sta=5029.4,5041.5
Exp/Cntr=0.3,0.1

Type RM Length L Ch R = 1,6197,839,839,839
BEGIN DESCRIPTION:
Steel Creek 11.0
END DESCRIPTION:
XS GIS Cut Line= 3
      1958525.01     13897375.01      1957338.92     13896872.38
      1956125.00     13896475.00
#Sta/Elev= 30
  3697.7 1563.50  3719.4 1555.82  3736.6 1551.55  3752.0 1550.46  3773.7 1545.17
  3790.0 1544.06  3871.5 1537.36  3960.3 1533.39  4051.9 1530.99  4246.7 1529.02
  4400.4 1529.67  4414.9 1528.06  4682.5 1528.22  4835.4 1521.46  4957.6 1519.29
  4972.2 1517.21  4972.7 1516.71  4986.3 1517.21  5000.5 1519.26  5058.1 1518.74
  5147.9 1522.62  5389.9 1526.94  5504.1 1530.55  5509.4 1529.59  5807.3 1538.81
  5988.9 1546.64  6073.8 1549.69  6105.4 1553.81  6175.2 1557.60  6263.2 1562.71
#Mann=12,-1,0
  3697.7    0.07       0  3736.6     0.1       0  3790.0    0.07       0
  3960.3   0.035       0  4051.9    0.07       0  4246.7   0.035       0
  4414.9    0.07       0  4972.2    0.05       0  4986.3    0.07       0
  5807.3    0.07       0  5988.9     0.1       0  6175.2    0.07       0
Bank Sta=4972.2,4986.3
Exp/Cntr=0.3,0.1

Type RM Length L Ch R = 1,5358,452,452,452
BEGIN DESCRIPTION:
Steel Creek 10.0
END DESCRIPTION:
XS GIS Cut Line= 3
      1958775.00     13896775.00      1956975.00     13896175.00
      1956474.99     13896325.00
#Sta/Elev= 30
  3102.2 1575.78  3154.9 1573.49  3165.5 1570.68  3179.4 1564.07  3186.5 1560.30
  3197.1 1557.14  3249.8 1545.10  3418.4 1533.12  3466.2 1530.94  3567.4 1526.96
  3569.0 1526.92  3774.7 1523.82  3877.5 1522.55  4076.6 1522.07  4103.6 1521.59
  4136.3 1519.03  4288.7 1517.51  4391.5 1517.96  4674.6 1517.46  4879.3 1515.47
  4946.9 1515.73  4967.9 1514.02  4971.4 1512.10  4971.9 1511.60  4985.6 1512.10
  4989.0 1515.01  5054.4 1519.74  5263.2 1526.00  5427.6 1534.87  5521.6 1541.41
#Mann=15,-1,0
  3102.2    0.07       0  3179.4     0.1       0  3466.2   0.033       0
  3567.4    0.07       0  3569.0   0.033       0  3774.7    0.07       0
  3877.5   0.035       0  4076.6    0.07       0  4136.3   0.035       0
  4288.7    0.07       0  4391.5   0.035       0  4674.6    0.07       0
  4879.3     0.1       0  4971.4    0.05       0  4985.6     0.1       0
Bank Sta=4971.4,4985.6
Exp/Cntr=0.3,0.1

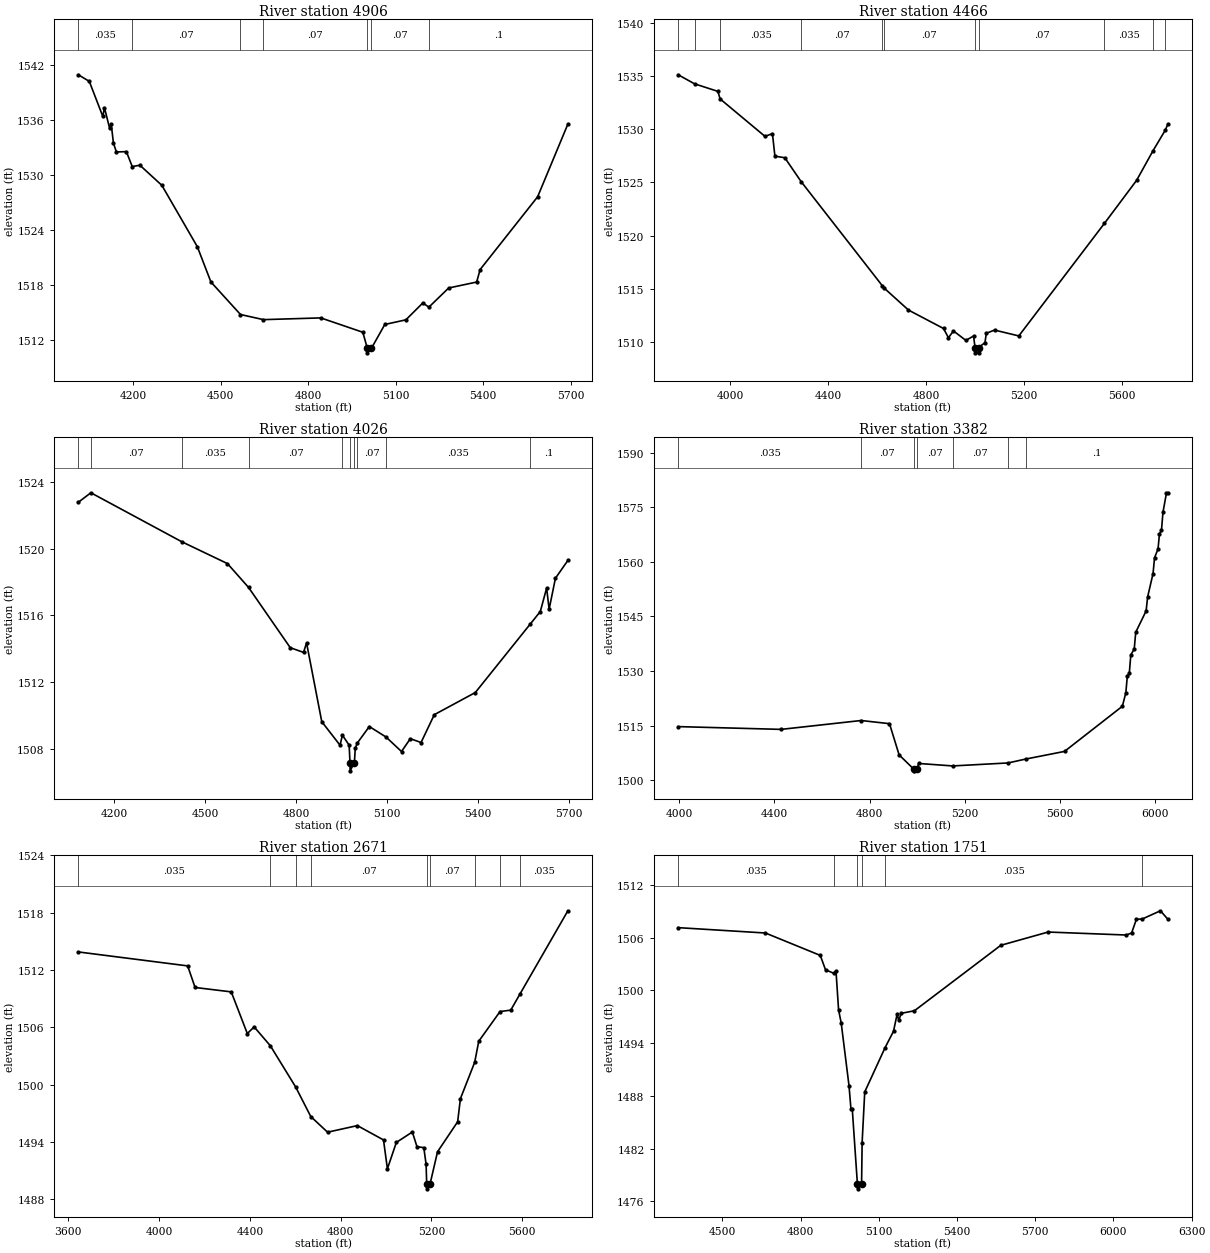
Type RM Length L Ch R = 1,4906,440,440,440
BEGIN DESCRIPTION:
Steel Creek 9.0
END DESCRIPTION:
XS GIS Cut Line= 3
      1958024.99     13896175.00      1957125.00     13895775.00
      1956525.00     13896125.00
#Sta/Elev= 30
  4011.3 1540.95  4048.9 1540.23  4095.4 1536.39  4100.9 1537.36  4118.7 1535.09
  4124.1 1535.57  4131.7 1533.48  4141.9 1532.51  4176.1 1532.55  4196.2 1530.92
  4222.6 1531.06  4297.9 1528.86  4419.6 1522.15  4466.1 1518.30  4567.6 1514.74
  4646.4 1514.18  4843.0 1514.37  4987.3 1512.80  5002.7 1511.05  5003.2 1510.55
  5016.9 1511.05  5062.7 1513.65  5135.1 1514.16  5193.0 1516.00  5214.0 1515.55
  5281.9 1517.64  5377.8 1518.29  5389.8 1519.66  5587.0 1527.61  5690.8 1535.56
#Mann=7,-1,0
  4011.3   0.035       0  4196.2    0.07       0  4567.6   0.035       0
  4646.4    0.07       0  5002.7    0.05       0  5016.9    0.07       0
  5214.0     0.1       0
Bank Sta=5002.7,5016.9
Exp/Cntr=0.3,0.1

Type RM Length L Ch R = 1,4466,440,440,440
BEGIN DESCRIPTION:
Steel Creek 8.0
END DESCRIPTION:
XS GIS Cut Line= 4
      1958245.03     13895566.03      1957092.80     13895385.62
      1956981.47     13895418.53      1956475.01     13895924.99
#Sta/Elev= 30
  3787.4 1535.12  3854.0 1534.27  3949.4 1533.56  3958.5 1532.85  4141.7 1529.33
  4172.1 1529.59  4182.2 1527.47  4222.7 1527.32  4289.4 1525.07  4621.3 1515.27
  4625.6 1515.12  4727.5 1513.00  4870.5 1511.27  4890.7 1510.40  4911.0 1511.04
  4961.8 1510.15  4993.1 1510.56  4999.3 1509.48  4999.8 1508.98  5013.4 1508.98
  5013.9 1509.48  5039.8 1509.94  5045.2 1510.82  5078.9 1511.12  5177.9 1510.57
  5527.4 1521.15  5658.7 1525.19  5725.1 1527.95  5776.3 1529.93  5786.0 1530.47
#Mann=11,-1,0
  3787.4   0.035       0  3854.0    0.07       0  3958.5   0.035       0
  4289.4    0.07       0  4621.3   0.035       0  4625.6    0.07       0
  4999.3    0.05       0  5013.9    0.07       0  5527.4   0.035       0
  5725.1     0.1       0  5776.3    0.07       0
Bank Sta=4999.3,5013.9
Exp/Cntr=0.3,0.1

Type RM Length L Ch R = 1,4026,644,644,644
BEGIN DESCRIPTION:
Steel Creek 7.0
END DESCRIPTION:
XS GIS Cut Line= 3
      1957844.99     13895087.16      1956925.00     13895025.00
      1956376.54     13895444.19
#Sta/Elev= 30
  4082.7 1522.78  4124.0 1523.35  4423.5 1520.41  4573.8 1519.10  4643.3 1517.67
  4780.8 1514.05  4824.4 1513.77  4834.4 1514.34  4884.5 1509.61  4944.6 1508.20
  4952.5 1508.80  4974.7 1508.20  4977.4 1507.16  4977.9 1506.66  4992.0 1507.16
  4994.8 1508.02  5002.0 1508.34  5041.1 1509.32  5096.1 1508.69  5147.1 1507.82
  5176.2 1508.59  5211.5 1508.36  5255.1 1510.03  5390.2 1511.36  5570.7 1515.46
  5604.2 1516.22  5625.1 1517.63  5633.3 1516.36  5654.1 1518.22  5695.1 1519.29
#Mann=10,-1,0
  4082.7   0.035       0  4124.0    0.07       0  4423.5   0.035       0
  4643.3    0.07       0  4952.5   0.035       0  4977.4   0.035       0
  4992.0   0.035       0  5002.0    0.07       0  5096.1   0.035       0
  5570.7     0.1       0
Bank Sta=4977.4,4992
Exp/Cntr=0.3,0.1

Type RM Length L Ch R = 1,3382,711,711,711
BEGIN DESCRIPTION:
Steel Creek 6.0
END DESCRIPTION:
XS GIS Cut Line= 3
      1957682.15     13894327.01      1956694.73     13894489.23
      1956056.14     13895333.96
#Sta/Elev= 30
  3995.0 1514.71  4427.9 1513.95  4764.7 1516.39  4883.9 1515.52  4924.4 1506.93
  4985.6 1503.05  4986.1 1502.55  5000.3 1503.05  5006.3 1504.58  5149.9 1503.90
  5382.8 1504.72  5456.2 1505.78  5620.2 1507.89  5863.7 1520.31  5878.3 1524.05
  5884.5 1528.60  5892.8 1529.36  5899.1 1534.41  5913.6 1536.08  5919.9 1540.66
  5963.6 1546.53  5969.9 1550.37  5992.7 1556.81  5999.0 1561.16  6013.5 1563.51
  6019.8 1567.74  6028.1 1568.64  6034.4 1573.63  6048.9 1578.88  6054.6 1579.01
#Mann=7,-1,0
  3995.0   0.035       0  4764.7    0.07       0  4985.6   0.035       0
  5000.3    0.07       0  5149.9    0.07       0  5382.8   0.035       0
  5456.2     0.1       0
Bank Sta=4985.6,5000.3
Exp/Cntr=0.3,0.1

Type RM Length L Ch R = 1,2671,920,920,920
BEGIN DESCRIPTION:
Steel Creek 5.0
END DESCRIPTION:
XS GIS Cut Line= 3
      1957681.76     13894202.70      1956351.15     13894011.68
      1955545.42     13893908.98
#Sta/Elev= 30
  3644.3 1513.89  4125.9 1512.43  4158.6 1510.17  4317.9 1509.71  4388.6 1505.35
  4418.9 1506.04  4490.1 1504.07  4601.7 1499.75  4668.2 1496.66  4742.2 1495.02
  4873.5 1495.71  4988.6 1494.21  5005.8 1491.19  5045.2 1493.95  5115.7 1495.04
  5135.9 1493.51  5166.1 1493.40  5176.2 1491.67  5178.9 1489.59  5179.4 1489.09
  5193.6 1489.59  5226.6 1492.97  5315.2 1496.11  5327.4 1498.53  5390.3 1502.34
  5408.1 1504.54  5501.9 1507.65  5549.2 1507.80  5590.3 1509.51  5800.8 1518.20
#Mann=9,-1,0
  3644.3   0.035       0  4490.1    0.07       0  4601.7   0.035       0
  4668.2    0.07       0  5178.9    0.05       0  5193.6    0.07       0
  5390.3   0.035       0  5501.9    0.07       0  5590.3   0.035       0
Bank Sta=5178.9,5193.6
Exp/Cntr=0.3,0.1

Type RM Length L Ch R = 1,1751,450,450,450
BEGIN DESCRIPTION:
Steel Creek 4.0
END DESCRIPTION:
XS GIS Cut Line= 3
      1957738.65     13893721.86      1957075.00     13893675.00
      1955866.97     13893569.86
#Sta/Elev= 30
  4330.4 1507.15  4664.9 1506.54  4875.4 1503.99  4895.5 1502.35  4926.3 1501.97
  4935.6 1502.24  4945.6 1497.78  4955.6 1496.31  4985.7 1489.13  4993.2 1486.46
  4998.2 1486.46  5017.9 1477.92  5018.4 1477.42  5033.8 1477.92  5035.9 1482.69
  5045.9 1488.45  5123.6 1493.47  5156.3 1495.36  5170.0 1497.28  5176.4 1496.63
  5186.4 1497.40  5236.6 1497.69  5567.9 1505.14  5749.4 1506.65  6049.7 1506.31
  6069.7 1506.55  6088.1 1508.11  6110.2 1508.13  6180.2 1509.07  6208.3 1508.12
#Mann=6,-1,0
  4330.4   0.035       0  4926.3    0.07       0  5017.9    0.05       0
  5033.8    0.07       0  5123.6   0.035       0  6110.2    0.07       0
Bank Sta=5017.9,5033.8
Exp/Cntr=0.3,0.1