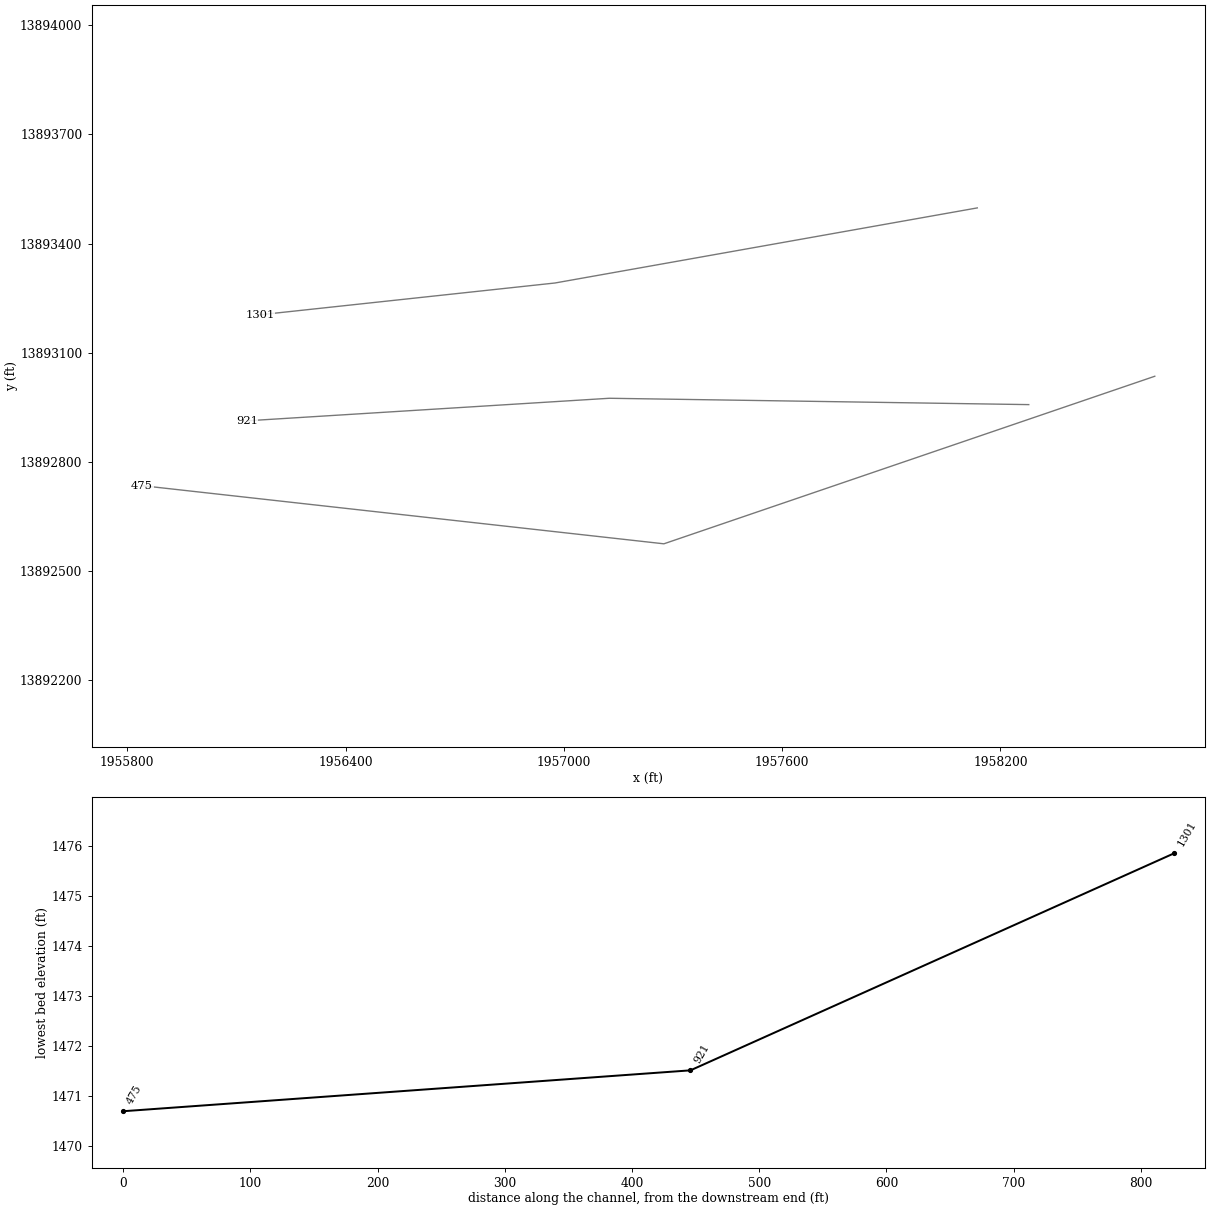
HEC-RAS study Steel Creek.prj: Steel Creek Base Level Engineering

--- Steel Creek.g01 (geometry) --- (continued)

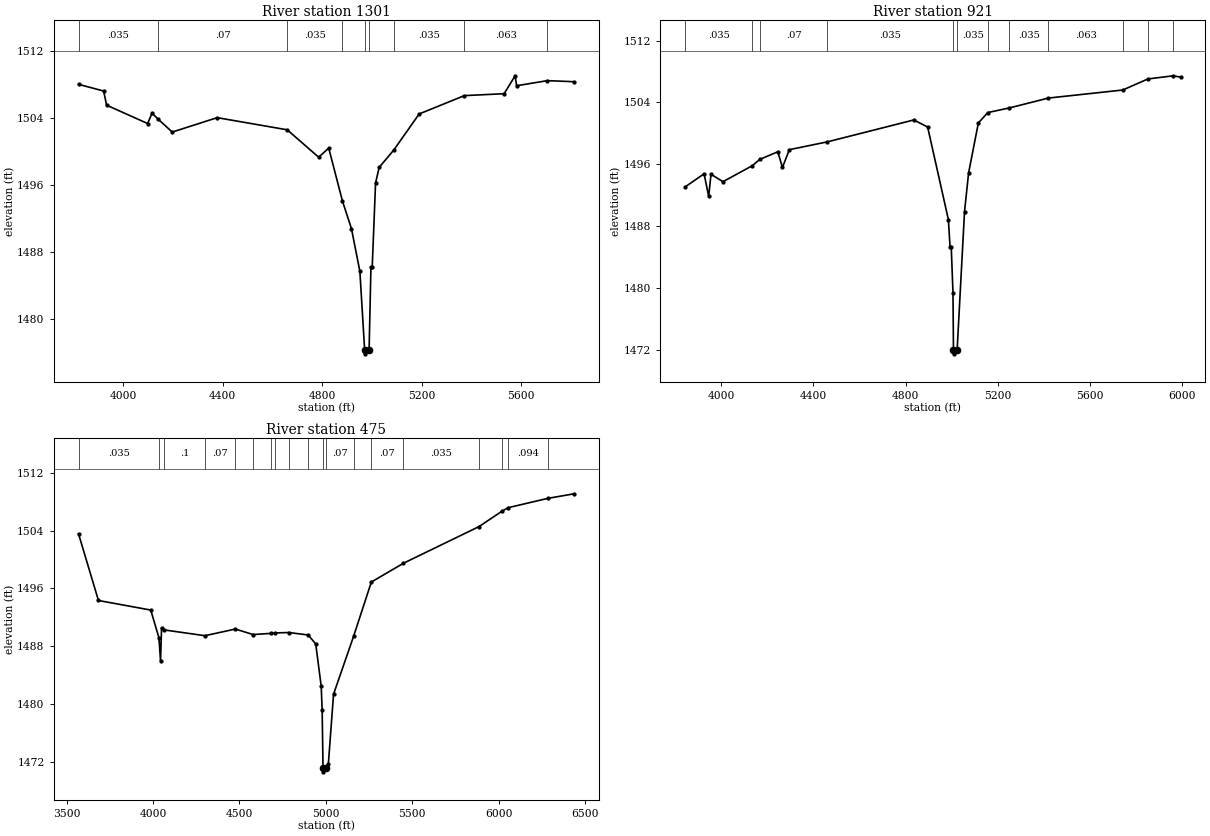
Type RM Length L Ch R = 1,1301,380,380,380
BEGIN DESCRIPTION:
Steel Creek 3.0
END DESCRIPTION:
XS GIS Cut Line= 3
      1958136.37     13893498.21      1956975.67     13893291.82
      1956164.77     13893204.43
#Sta/Elev= 30
  3819.7 1508.04  3920.7 1507.24  3932.8 1505.55  4097.7 1503.36  4115.6 1504.59
  4139.0 1503.91  4196.9 1502.34  4377.7 1504.06  4659.4 1502.61  4786.0 1499.34
  4826.6 1500.42  4881.9 1494.09  4918.0 1490.81  4951.9 1485.71  4971.0 1476.36
  4971.5 1475.86  4986.9 1476.36  4989.1 1476.46  4996.4 1486.17  5001.5 1486.17
  5015.0 1496.25  5029.5 1498.12  5088.5 1500.20  5190.4 1504.50  5372.2 1506.69
  5532.4 1506.92  5576.6 1509.06  5582.6 1507.87  5706.5 1508.48  5814.2 1508.35
#Mann=9,-1,0
  3819.7   0.035       0  4139.0    0.07       0  4659.4   0.035       0
  4881.9     0.1       0  4971.0    0.05       0  4986.9     0.1       0
  5088.5   0.035       0  5372.2   0.063       0  5706.5   0.035       0
Bank Sta=4971,4986.9
Exp/Cntr=0.3,0.1

Type RM Length L Ch R = 1,921,446,446,446
BEGIN DESCRIPTION:
Steel Creek 2.0
END DESCRIPTION:
XS GIS Cut Line= 3
      1958277.85     13892957.55      1957125.00     13892975.00
      1956129.00     13892913.05
#Sta/Elev= 30
  3842.5 1493.07  3925.4 1494.78  3945.4 1491.87  3955.4 1494.72  4007.4 1493.76
  4134.3 1495.82  4167.1 1496.64  4245.4 1497.63  4265.4 1495.60  4295.4 1497.90
  4460.5 1498.91  4835.5 1501.74  4895.5 1500.83  4985.5 1488.87  4993.0 1485.27
  4998.0 1485.27  5005.5 1479.43  5007.6 1472.01  5008.1 1471.51  5023.5 1472.01
  5055.6 1489.89  5073.3 1494.90  5115.7 1501.36  5157.0 1502.70  5249.6 1503.29
  5419.6 1504.57  5742.3 1505.61  5851.4 1507.04  5961.6 1507.45  5993.4 1507.27
#Mann=12,-1,0
  3842.5   0.035       0  4134.3     0.1       0  4167.1    0.07       0
  4460.5   0.035       0  5007.6   0.035       0  5023.5   0.035       0
  5157.0   0.063       0  5249.6   0.035       0  5419.6   0.063       0
  5742.3   0.094       0  5851.4   0.063       0  5961.6   0.094       0
Bank Sta=5007.6,5023.5
Exp/Cntr=0.3,0.1

Type RM Length L Ch R = 1,475,0,0,0
BEGIN DESCRIPTION:
Steel Creek 1.0
END DESCRIPTION:
XS GIS Cut Line= 3
      1958624.21     13893035.51      1957275.00     13892575.00
      1955841.11     13892734.78
#Sta/Elev= 30
  3569.0 1503.55  3684.4 1494.34  3987.0 1493.02  4034.7 1489.17  4043.7 1485.98
  4049.7 1490.59  4064.4 1490.28  4300.8 1489.48  4476.5 1490.40  4579.5 1489.64
  4682.6 1489.80  4705.9 1489.86  4785.6 1489.92  4898.2 1489.58  4941.8 1488.34
  4973.5 1482.51  4979.0 1479.21  4984.0 1471.19  4984.5 1470.69  4999.9 1471.19
  5014.8 1471.75  5044.9 1481.40  5161.2 1489.42  5263.7 1496.89  5449.4 1499.48
  5887.5 1504.55  6022.4 1506.71  6055.4 1507.15  6285.6 1508.44  6437.4 1509.07
#Mann=19,-1,0
  3569.0   0.035       0  4034.7     0.1       0  4064.4     0.1       0
  4300.8    0.07       0  4476.5   0.035       0  4579.5    0.07       0
  4682.6     0.1       0  4705.9    0.07       0  4785.6   0.035       0
  4898.2    0.07       0  4984.0    0.05       0  4999.9    0.07       0
  5161.2   0.035       0  5263.7    0.07       0  5449.4   0.035       0
  5887.5   0.094       0  6022.4   0.063       0  6055.4   0.094       0
  6285.6   0.035       0
Bank Sta=4984,4999.9
Exp/Cntr=0.3,0.1

Chan Stop Cuts=-1