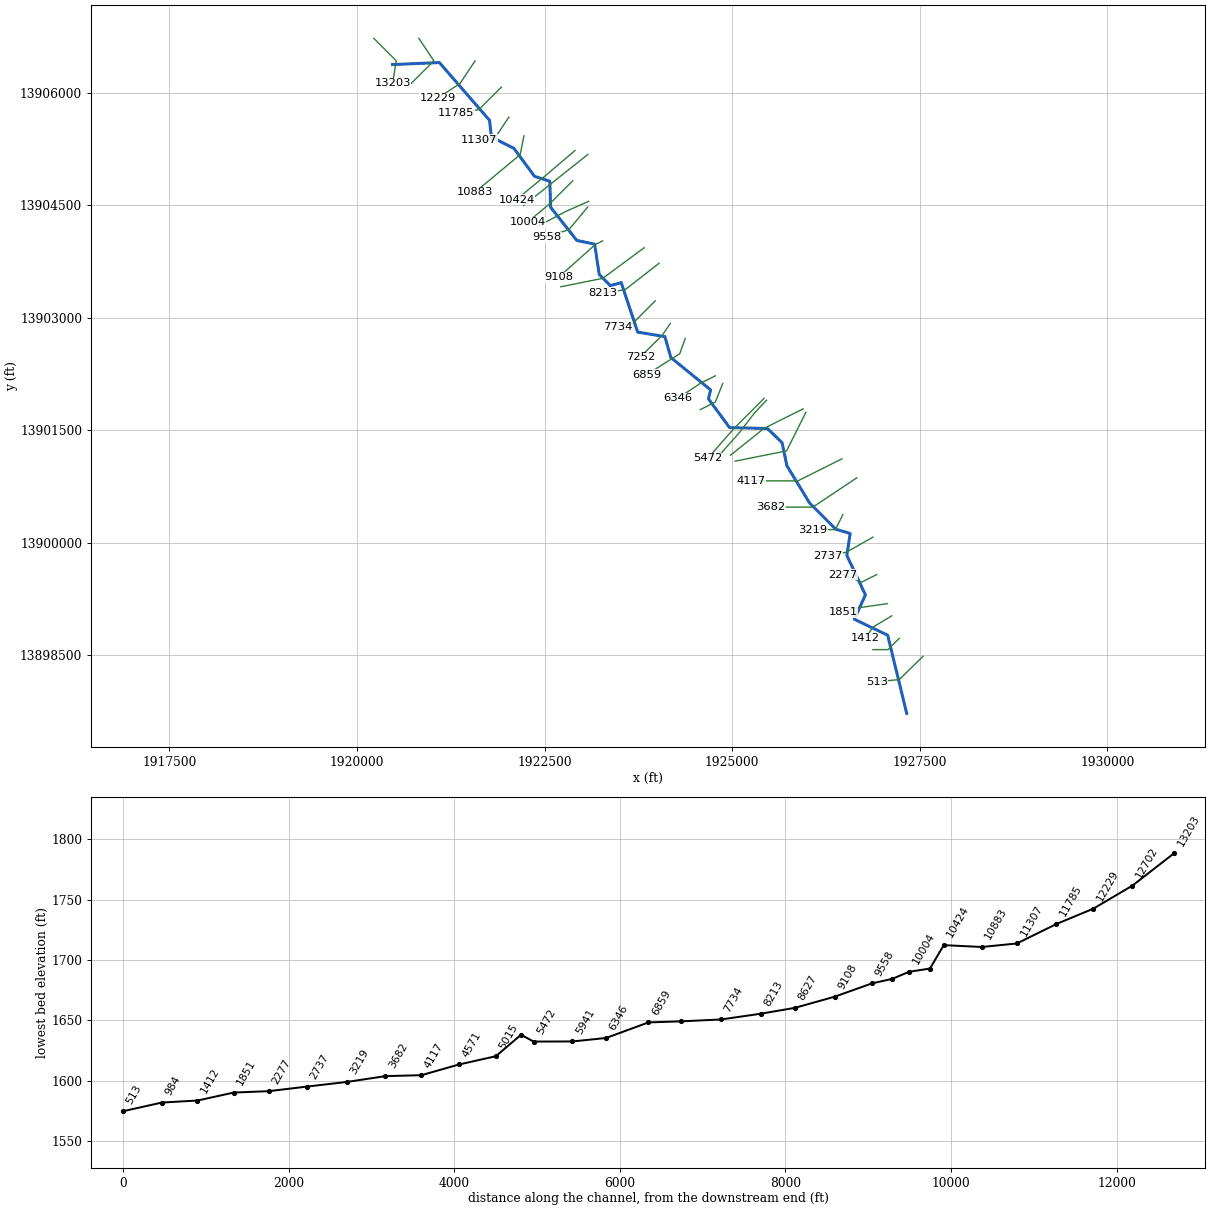
--- Stone Creek.prj (project) ---

Proj Title=Stone Creek Base Level Engineering
Current Plan=p01
Default Exp/Contr=0.3,0.1
English Units
Geom File=g01
Flow File=f01
Plan File=p01
BEGIN DESCRIPTION:
Stone Creek
END DESCRIPTION:

--- Stone Creek.p01 (plan) ---

Plan Title=Multiple Run
Short Identifier=Multiple
Geom File=g01
Flow File=f01
Subcritical Flow
K Sum by GR= 0
Std Step Tol= 0.01
Critical Tol= 0.01
Num of Std Step Trials= 20
Max Error Tol= 0.3
Flow Tol Ratio= 0.001
Split Flow NTrial= 30
Split Flow Tol= 0.02
Split Flow Ratio= 0.02
Log Output Level= 0
Friction Slope Method= 1
Unsteady Friction Slope Method= 2
Unsteady Bridges Friction Slope Method= 1
Parabolic Critical Depth
Global Vel Dist=  1 , 1 , 1
Global Log Level= 0
CheckData=True
Encroach Param= -1, 0, 0, 0
BEGIN DESCRIPTION:
Multiple Run
END DESCRIPTION:

--- Stone Creek.f01 (steady flow) ---

Flow Title=Multiple
Number of Profiles=7
Profile Names=10-year,25-year,50-year,1pct_min,100-year,1pct_plu,500-year
River Rch & RM= Stone Creek,Reach-1,13203
     749    1255    1732    1160    2314    4617    4069
River Rch & RM= Stone Creek,Reach-1,10424
    1478    2571    3633    2481    4950    9876    9079
River Rch & RM= Stone Creek,Reach-1,5472
    2115    3723    5302    3644    7270   14506   13508
Boundary for River Rch & Prof#=Stone Creek,Reach-1,1
Up Type=0
Dn Type=3
Dn Slope=0.005
Boundary for River Rch & Prof#=Stone Creek,Reach-1,2
Up Type=0
Dn Type=3
Dn Slope=0.005
Boundary for River Rch & Prof#=Stone Creek,Reach-1,3
Up Type=0
Dn Type=3
Dn Slope=0.005
Boundary for River Rch & Prof#=Stone Creek,Reach-1,4
Up Type=0
Dn Type=3
Dn Slope=0.005
Boundary for River Rch & Prof#=Stone Creek,Reach-1,5
Up Type=0
Dn Type=3
Dn Slope=0.005
Boundary for River Rch & Prof#=Stone Creek,Reach-1,6
Up Type=0
Dn Type=3
Dn Slope=0.005
Boundary for River Rch & Prof#=Stone Creek,Reach-1,7
Up Type=0
Dn Type=3
Dn Slope=0.005

--- Stone Creek.g01 (geometry) ---

Geom Title=Existing Conditions

River Reach=Stone Creek,Reach-1
Reach XY= 30
      1920475.00     13906375.00      1921098.53     13906402.14
      1921767.19     13905631.19      1921791.41     13905408.20
      1922091.71     13905258.37      1922365.29     13904885.75
      1922569.97     13904819.92      1922580.47     13904472.55
      1922930.44     13904030.18      1923167.00     13903981.39
      1923228.54     13903576.46      1923376.64     13903428.13
      1923521.34     13903467.57      1923741.45     13902807.86
      1924102.69     13902748.83      1924182.86     13902468.83
      1924711.88     13902038.24      1924684.03     13901917.99
      1924964.89     13901535.30      1925469.14     13901522.95
      1925664.24     13901334.68      1925728.75     13901026.55
      1926030.62     13900530.62      1926380.41     13900180.18
      1926571.64     13900123.75      1926527.34     13899830.52
      1926775.36     13899304.79      1926627.07     13898980.24
      1927071.49     13898766.52      1927325.00     13897725.00

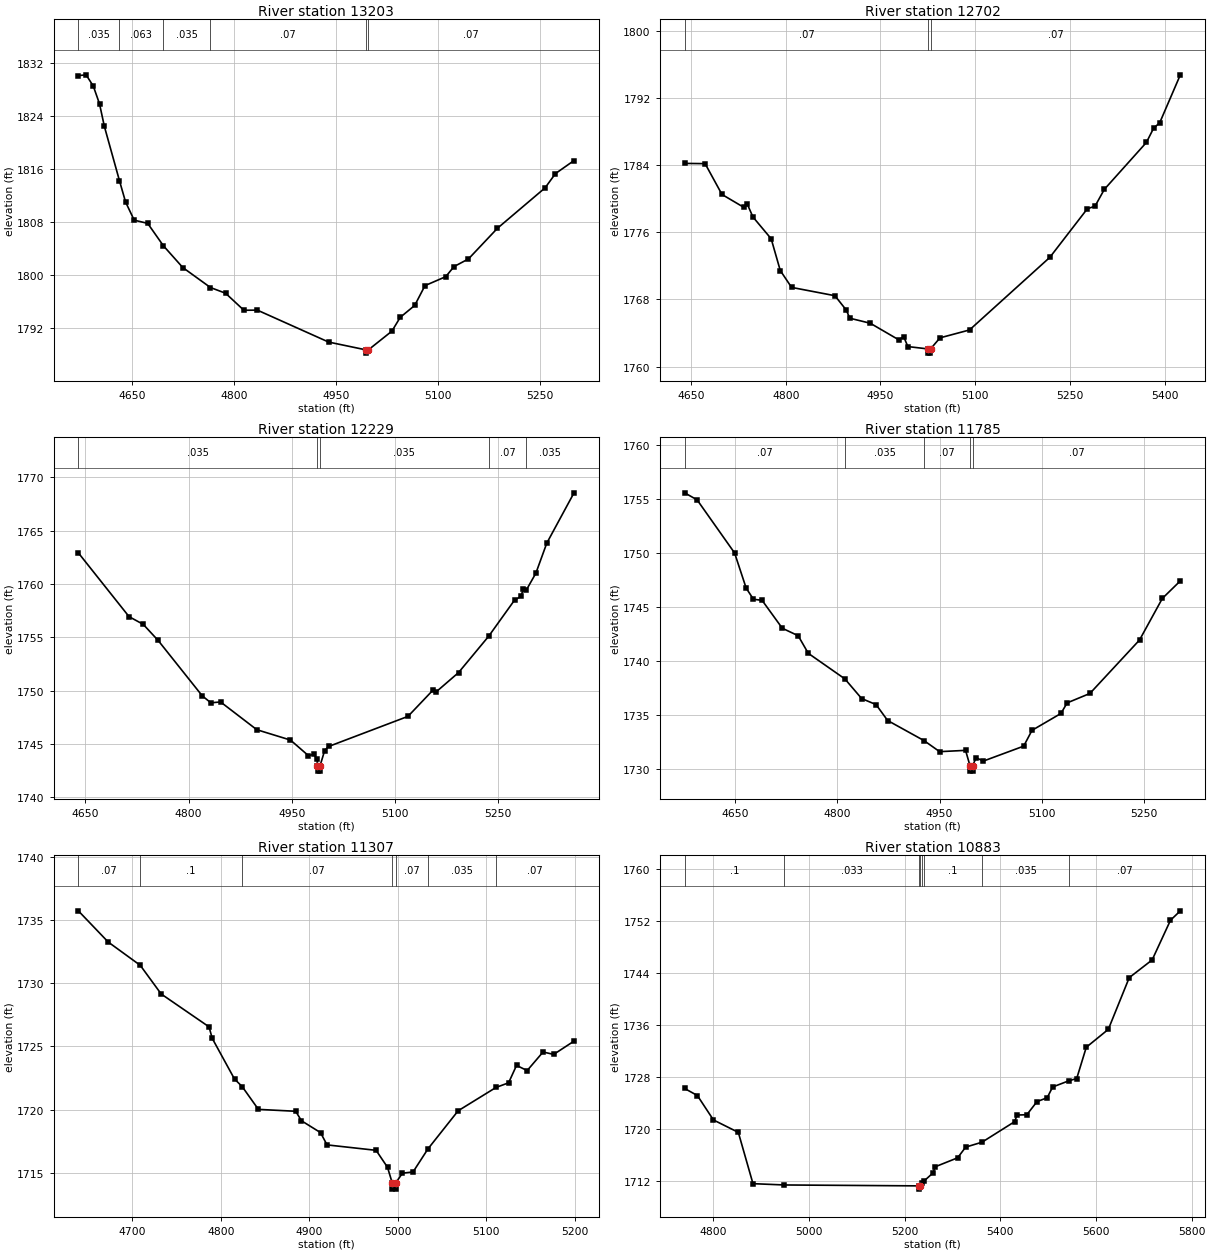
Type RM Length L Ch R = 1,13203,501,501,501
BEGIN DESCRIPTION:
Stone Creek 29.0
END DESCRIPTION:
XS GIS Cut Line= 3
      1920224.99     13906725.01      1920525.00     13906425.00
      1920475.00     13906125.02
#Sta/Elev= 30
  4571.4 1830.17  4582.8 1830.29  4593.4 1828.59  4602.6 1825.89  4609.6 1822.53
  4631.9 1814.29  4640.8 1811.10  4653.5 1808.35  4673.3 1807.87  4696.3 1804.50
  4724.9 1801.20  4765.6 1798.18  4787.8 1797.32  4814.7 1794.75  4834.5 1794.77
  4939.2 1789.95  4993.7 1788.78  4993.9 1788.28  4997.7 1788.78  5032.2 1791.60
  5044.4 1793.68  5065.7 1795.48  5080.8 1798.47  5111.3 1799.82  5123.4 1801.34
  5144.7 1802.50  5187.3 1807.13  5257.3 1813.23  5272.5 1815.38  5299.8 1817.35
#Mann=6,-1,0
  4571.4   0.035       0  4631.9   0.063       0  4696.3   0.035       0
  4765.6    0.07       0  4993.7    0.05       0  4997.7    0.07       0
Bank Sta=4993.7,4997.7
Exp/Cntr=0.3,0.1

Type RM Length L Ch R = 1,12702,473,473,473
BEGIN DESCRIPTION:
Stone Creek 28.0
END DESCRIPTION:
XS GIS Cut Line= 3
      1920825.03     13906724.96      1921025.00     13906425.00
      1920724.98     13906124.98
#Sta/Elev= 30
  4640.0 1784.20  4672.4 1784.17  4699.1 1780.50  4733.8 1778.96  4739.2 1779.35
  4748.1 1777.82  4777.0 1775.22  4791.4 1771.44  4809.3 1769.43  4877.9 1768.44
  4896.0 1766.72  4901.4 1765.76  4933.9 1765.16  4978.9 1763.19  4986.8 1763.56
  4993.4 1762.38  5025.3 1762.10  5025.6 1761.60  5029.1 1761.60  5029.3 1762.10
  5044.3 1763.42  5091.0 1764.36  5218.2 1773.01  5277.6 1778.80  5289.7 1779.10
  5304.5 1781.11  5371.0 1786.69  5382.4 1788.38  5392.2 1789.05  5424.8 1794.75
#Mann=3,-1,0
  4640.0    0.07       0  5025.3    0.05       0  5029.3    0.07       0
Bank Sta=5025.3,5029.3
Exp/Cntr=0.3,0.1

Type RM Length L Ch R = 1,12229,444,444,444
BEGIN DESCRIPTION:
Stone Creek 27.0
END DESCRIPTION:
XS GIS Cut Line= 3
      1921574.98     13906424.97      1921375.00     13906125.00
      1921075.06     13905925.04
#Sta/Elev= 30
  4639.7 1762.91  4713.5 1756.93  4734.1 1756.21  4755.8 1754.70  4820.0 1749.51
  4832.5 1748.86  4846.6 1748.94  4899.3 1746.34  4948.3 1745.37  4974.2 1743.92
  4982.2 1744.03  4987.2 1743.58  4987.3 1742.96  4987.6 1742.46  4991.1 1742.46
  4991.3 1742.96  4998.0 1744.39  5003.8 1744.77  5119.2 1747.59  5156.0 1750.08
  5160.3 1749.89  5192.7 1751.69  5236.5 1755.09  5274.2 1758.48  5283.6 1758.83
  5286.9 1759.56  5291.2 1759.41  5305.2 1761.00  5321.1 1763.82  5360.7 1768.53
#Mann=5,-1,0
  4639.7   0.035       0  4987.3   0.035       0  4991.3   0.035       0
  5236.5    0.07       0  5291.2   0.035       0
Bank Sta=4987.3,4991.3
Exp/Cntr=0.3,0.1

Type RM Length L Ch R = 1,11785,478,478,478
BEGIN DESCRIPTION:
Stone Creek 26.0
END DESCRIPTION:
XS GIS Cut Line= 3
      1921924.97     13906074.97      1921625.00     13905775.00
      1921324.96     13905724.99
#Sta/Elev= 30
  4575.5 1755.56  4593.8 1754.91  4648.9 1750.00  4665.9 1746.75  4676.6 1745.72
  4689.3 1745.62  4719.0 1743.04  4742.3 1742.35  4757.2 1740.72  4810.9 1738.36
  4835.6 1736.54  4856.8 1735.98  4873.8 1734.51  4927.3 1732.65  4950.2 1731.63
  4988.3 1731.75  4994.8 1730.33  4995.1 1729.83  4998.6 1729.83  4998.8 1730.33
  5003.7 1731.07  5014.5 1730.76  5073.7 1732.14  5085.9 1733.60  5128.4 1735.16
  5137.6 1736.14  5171.0 1737.01  5243.9 1741.95  5277.5 1745.80  5303.9 1747.42
#Mann=5,-1,0
  4575.5    0.07       0  4810.9   0.035       0  4927.3    0.07       0
  4994.8    0.05       0  4998.8    0.07       0
Bank Sta=4994.8,4998.8
Exp/Cntr=0.3,0.1

Type RM Length L Ch R = 1,11307,424,424,424
BEGIN DESCRIPTION:
Stone Creek 25.0
END DESCRIPTION:
XS GIS Cut Line= 3
      1922024.97     13905674.96      1921825.00     13905375.00
      1921625.01     13905375.00
#Sta/Elev= 30
  4638.8 1735.72  4672.6 1733.25  4708.8 1731.41  4732.5 1729.14  4786.6 1726.54
  4790.2 1725.63  4815.4 1722.41  4824.0 1721.82  4842.4 1720.01  4884.6 1719.86
  4891.1 1719.11  4912.7 1718.17  4920.0 1717.20  4975.5 1716.77  4988.4 1715.43
  4993.7 1714.20  4994.0 1713.70  4997.5 1713.70  4997.7 1714.20  5005.3 1714.96
  5017.3 1715.06  5034.2 1716.89  5068.3 1719.90  5111.2 1721.75  5125.3 1722.11
  5134.3 1723.49  5146.3 1723.08  5164.3 1724.55  5176.3 1724.36  5199.3 1725.41
#Mann=7,-1,0
  4638.8    0.07       0  4708.8     0.1       0  4824.0    0.07       0
  4993.7    0.05       0  4997.7    0.07       0  5034.2   0.035       0
  5111.2    0.07       0
Bank Sta=4993.7,4997.7
Exp/Cntr=0.3,0.1

Type RM Length L Ch R = 1,10883,459,459,459
BEGIN DESCRIPTION:
Stone Creek 24.0
END DESCRIPTION:
XS GIS Cut Line= 3
      1922225.01     13905425.04      1922175.00     13905175.00
      1921575.01     13904675.01
#Sta/Elev= 30
  4740.4 1726.26  4767.0 1725.18  4800.6 1721.42  4852.6 1719.51  4883.2 1711.62
  4948.8 1711.42  5229.3 1711.28  5229.5 1710.78  5233.3 1711.28  5236.9 1711.79
  5241.1 1712.05  5259.6 1713.28  5263.8 1714.21  5311.0 1715.60  5327.7 1717.24
  5361.9 1718.00  5429.9 1721.15  5435.3 1722.18  5455.5 1722.22  5476.8 1724.24
  5498.1 1724.84  5509.5 1726.49  5543.9 1727.46  5559.8 1727.79  5579.8 1732.60
  5625.9 1735.36  5669.6 1743.31  5717.5 1746.04  5755.8 1752.14  5776.4 1753.59
#Mann=8,-1,0
  4740.4     0.1       0  4948.8   0.033       0  5229.3   0.033       0
  5233.3   0.033       0  5236.9    0.07       0  5241.1     0.1       0
  5361.9   0.035       0  5543.9    0.07       0
Bank Sta=5229.3,5233.3
Exp/Cntr=0.3,0.1

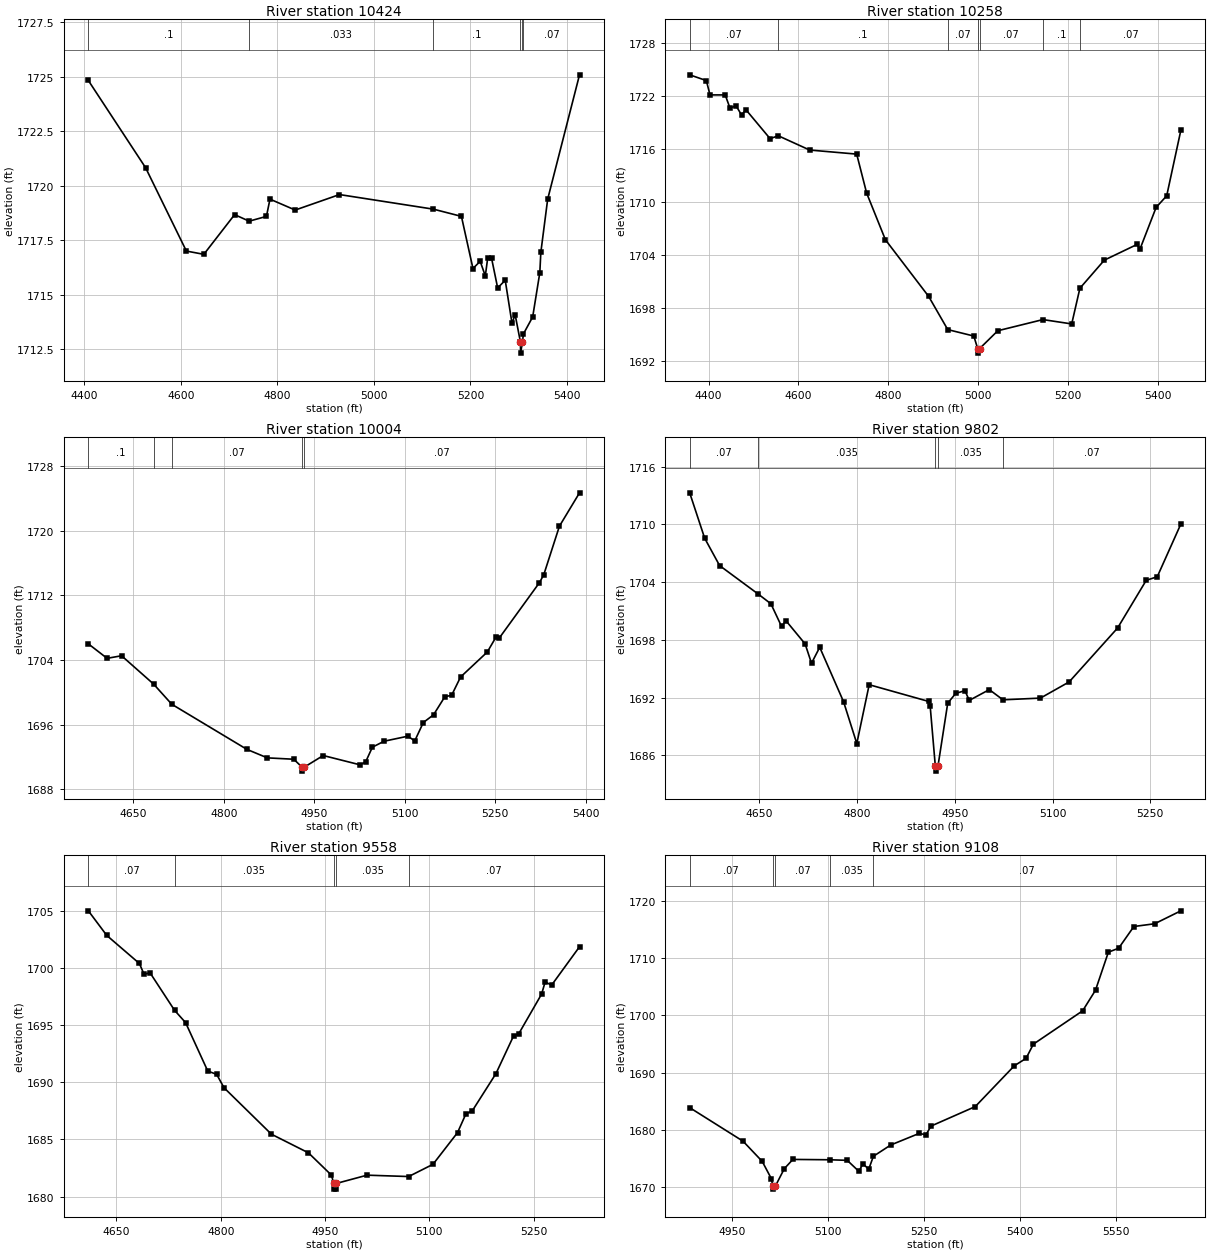
Type RM Length L Ch R = 1,10424,166,166,166
BEGIN DESCRIPTION:
Stone Creek 23.0
END DESCRIPTION:
XS GIS Cut Line= 3
      1922905.46     13905229.00      1922497.51     13904881.81
      1922125.07     13904575.06
#Sta/Elev= 30
  4408.0 1724.83  4526.7 1720.83  4611.2 1717.01  4647.4 1716.86  4711.2 1718.68
  4741.4 1718.38  4777.2 1718.60  4784.5 1719.39  4836.8 1718.89  4928.6 1719.60
  5123.5 1718.93  5181.4 1718.60  5205.3 1716.21  5220.3 1716.54  5230.9 1715.87
  5235.8 1716.68  5243.9 1716.68  5256.5 1715.32  5272.2 1715.67  5286.3 1713.69
  5292.7 1714.10  5303.8 1712.83  5304.0 1712.33  5307.8 1712.83  5309.9 1713.21
  5329.1 1713.99  5343.9 1716.02  5346.0 1716.95  5360.2 1719.39  5426.2 1725.09
#Mann=6,-1,0
  4408.0     0.1       0  4741.4   0.033       0  5123.5     0.1       0
  5303.8   0.033       0  5307.8     0.1       0  5309.9    0.07       0
Bank Sta=5303.8,5307.8
Exp/Cntr=0.3,0.1

Type RM Length L Ch R = 1,10258,254,254,254
BEGIN DESCRIPTION:
Mapping XS 31e6bf09
END DESCRIPTION:
XS GIS Cut Line= 2
      1923077.98     13905178.10      1922223.07     13904497.73
#Sta/Elev= 30
  4358.0 1724.36  4395.0 1723.71  4403.2 1722.09  4437.0 1722.09  4447.7 1720.59
  4461.0 1720.87  4473.3 1719.83  4483.2 1720.41  4536.8 1717.15  4555.2 1717.47
  4624.9 1715.86  4729.5 1715.40  4751.6 1711.00  4793.4 1705.72  4889.7 1699.31
  4932.0 1695.57  4990.0 1694.84  4998.7 1693.41  4998.9 1692.91  5002.7 1693.41
  5043.4 1695.44  5143.8 1696.70  5207.8 1696.21  5226.0 1700.24  5280.4 1703.42
  5353.5 1705.20  5359.4 1704.63  5395.6 1709.38  5419.1 1710.69  5450.6 1718.10
#Mann=7,-1,0
  4358.0    0.07       0  4555.2     0.1       0  4932.0    0.07       0
  4998.7    0.05       0  5002.7    0.07       0  5143.8     0.1       0
  5226.0    0.07       0
Bank Sta=4998.7,5002.7
Exp/Cntr=0.3,0.1

Type RM Length L Ch R = 1,10004,202,202,202
BEGIN DESCRIPTION:
Stone Creek 22.0
END DESCRIPTION:
XS GIS Cut Line= 3
      1922874.99     13904824.99      1922575.00     13904525.00
      1922275.05     13904275.04
#Sta/Elev= 30
  4575.2 1705.98  4606.3 1704.19  4630.3 1704.51  4683.5 1701.00  4713.6 1698.51
  4838.2 1692.93  4872.1 1691.88  4916.0 1691.71  4929.5 1690.74  4929.8 1690.24
  4933.5 1690.74  4964.8 1692.17  5026.4 1691.01  5035.4 1691.42  5046.3 1693.20
  5065.8 1693.94  5105.2 1694.56  5116.6 1693.98  5130.8 1696.25  5147.8 1697.21
  5166.6 1699.45  5177.7 1699.61  5192.6 1701.88  5236.9 1704.97  5251.0 1706.77
  5257.1 1706.73  5323.5 1713.56  5330.6 1714.53  5356.6 1720.54  5389.9 1724.66
#Mann=5,-1,0
  4575.2     0.1       0  4683.5   0.035       0  4713.6    0.07       0
  4929.5    0.05       0  4933.5    0.07       0
Bank Sta=4929.5,4933.5
Exp/Cntr=0.3,0.1

Type RM Length L Ch R = 1,9802,244,244,244
BEGIN DESCRIPTION:
Stone Creek 21.1
END DESCRIPTION:
XS GIS Cut Line= 4
      1923088.05     13904552.06      1922792.92     13904421.86
      1922627.99     13904335.06      1922410.93     13904222.19
#Sta/Elev= 30
  4543.2 1713.29  4566.2 1708.57  4589.1 1705.73  4648.7 1702.75  4667.8 1701.76
  4684.2 1699.40  4690.8 1700.01  4720.3 1697.59  4730.1 1695.58  4742.7 1697.24
  4779.3 1691.58  4799.6 1687.24  4818.6 1693.35  4910.0 1691.61  4912.2 1691.10
  4920.1 1684.87  4920.4 1684.37  4924.1 1684.87  4939.1 1691.43  4951.4 1692.45
  4965.5 1692.73  4972.2 1691.72  5002.9 1692.84  5023.9 1691.78  5081.4 1691.96
  5125.4 1693.64  5199.7 1699.24  5243.7 1704.20  5260.6 1704.57  5296.8 1710.05
#Mann=5,-1,0
  4543.2    0.07       0  4648.7   0.035       0  4920.1   0.035       0
  4924.1   0.035       0  5023.9    0.07       0
Bank Sta=4920.1,4924.1
Exp/Cntr=0.3,0.1

Type RM Length L Ch R = 1,9558,450,450,450
BEGIN DESCRIPTION:
Stone Creek 21.0
END DESCRIPTION:
XS GIS Cut Line= 3
      1923075.00     13904475.00      1922825.00     13904175.00
      1922525.04     13904075.01
#Sta/Elev= 30
  4609.5 1704.98  4636.0 1702.83  4682.9 1700.38  4689.7 1699.43  4698.2 1699.57
  4733.5 1696.29  4749.4 1695.21  4781.3 1690.98  4794.1 1690.69  4804.7 1689.52
  4872.9 1685.46  4926.2 1683.83  4959.3 1681.88  4962.5 1681.16  4962.8 1680.66
  4966.3 1680.66  4966.5 1681.16  5010.5 1681.88  5070.4 1681.76  5105.4 1682.83
  5140.7 1685.60  5152.6 1687.22  5162.1 1687.52  5196.0 1690.76  5221.4 1694.06
  5228.7 1694.23  5261.7 1697.71  5266.7 1698.76  5276.1 1698.49  5316.2 1701.84
#Mann=5,-1,0
  4609.5    0.07       0  4733.5   0.035       0  4962.5   0.035       0
  4966.5   0.035       0  5070.4    0.07       0
Bank Sta=4962.5,4966.5
Exp/Cntr=0.3,0.1

Type RM Length L Ch R = 1,9108,481,481,481
BEGIN DESCRIPTION:
Stone Creek 20.0
END DESCRIPTION:
XS GIS Cut Line= 3
      1923275.04     13904025.02      1923175.00     13903975.00
      1922685.49     13903537.75
#Sta/Elev= 30
  4883.7 1683.89  4967.2 1678.02  4997.1 1674.50  5011.6 1671.44  5013.6 1670.15
  5013.9 1669.65  5017.6 1670.15  5031.7 1673.23  5045.1 1674.84  5102.7 1674.78
  5130.1 1674.68  5148.3 1672.76  5154.7 1674.09  5163.7 1673.12  5171.0 1675.39
  5198.1 1677.36  5242.7 1679.39  5253.3 1679.14  5261.0 1680.66  5330.3 1684.07
  5391.4 1691.20  5409.8 1692.50  5421.2 1694.98  5498.3 1700.81  5518.4 1704.41
  5538.5 1711.05  5554.6 1711.75  5578.4 1715.54  5610.9 1716.02  5651.9 1718.28
#Mann=5,-1,0
  4883.7    0.07       0  5013.6    0.05       0  5017.6    0.07       0
  5102.7   0.035       0  5171.0    0.07       0
Bank Sta=5013.6,5017.6
Exp/Cntr=0.3,0.1

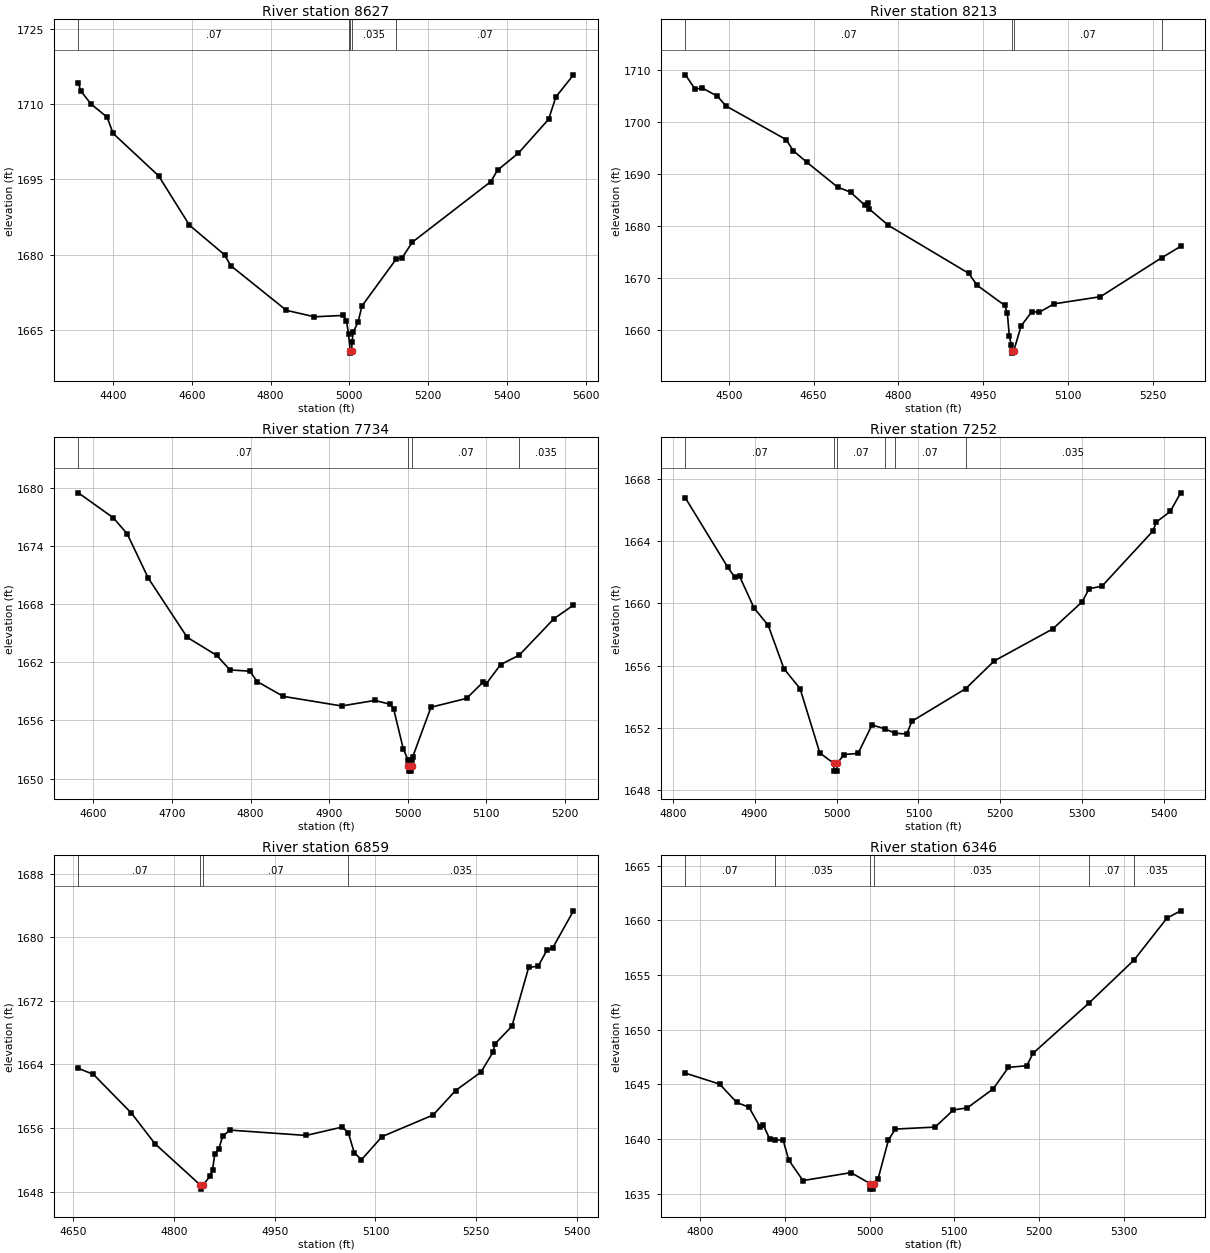
Type RM Length L Ch R = 1,8627,414,414,414
BEGIN DESCRIPTION:
Stone Creek 19.0
END DESCRIPTION:
XS GIS Cut Line= 3
      1923827.86     13903933.46      1923275.00     13903525.00
      1922717.30     13903413.08
#Sta/Elev= 30
  4312.3 1714.27  4318.3 1712.68  4344.4 1710.05  4385.4 1707.43  4400.5 1704.19
  4516.0 1695.73  4594.3 1685.89  4683.3 1679.99  4698.8 1677.84  4840.2 1668.92
  4911.4 1667.63  4983.9 1667.91  4992.5 1666.86  4997.9 1664.23  5001.9 1660.89
  5002.2 1660.39  5005.9 1660.89  5006.5 1662.51  5009.8 1664.58  5022.1 1666.60
  5031.9 1669.78  5118.3 1679.09  5133.9 1679.40  5159.8 1682.51  5358.7 1694.57
  5376.0 1696.87  5429.0 1700.27  5505.5 1707.01  5523.9 1711.46  5568.5 1715.86
#Mann=5,-1,0
  4312.3    0.07       0  4997.9   0.035       0  5001.9   0.035       0
  5005.9   0.035       0  5118.3    0.07       0
Bank Sta=5001.9,5005.9
Exp/Cntr=0.3,0.1

Type RM Length L Ch R = 1,8213,479,479,479
BEGIN DESCRIPTION:
Stone Creek 18.0
END DESCRIPTION:
XS GIS Cut Line= 3
      1924026.53     13903726.38      1923575.00     13903375.00
      1923274.98     13903325.00
#Sta/Elev= 30
  4423.2 1709.07  4440.1 1706.32  4453.0 1706.51  4479.4 1704.99  4494.8 1703.08
  4601.2 1696.61  4614.1 1694.45  4637.6 1692.28  4692.4 1687.46  4715.3 1686.49
  4740.2 1684.00  4745.7 1684.40  4748.8 1683.22  4782.1 1680.11  4924.1 1670.89
  4939.5 1668.55  4988.2 1664.69  4992.8 1663.15  4996.3 1658.83  4999.7 1657.12
  5000.3 1656.01  5000.5 1655.51  5004.3 1656.01  5017.2 1660.76  5036.2 1663.49
  5049.2 1663.37  5075.4 1664.99  5157.5 1666.37  5266.7 1673.91  5299.5 1676.06
#Mann=4,-1,0
  4423.2    0.07       0  5000.3    0.05       0  5004.3    0.07       0
  5266.7   0.035       0
Bank Sta=5000.3,5004.3
Exp/Cntr=0.3,0.1

Type RM Length L Ch R = 1,7734,482,482,482
BEGIN DESCRIPTION:
Stone Creek 17.0
END DESCRIPTION:
XS GIS Cut Line= 3
      1923975.02     13903225.02      1923675.00     13902925.00
      1923475.05     13902875.01
#Sta/Elev= 30
  4580.7 1679.51  4625.3 1676.93  4642.9 1675.28  4669.8 1670.70  4719.3 1664.59
  4756.8 1662.73  4773.8 1661.22  4799.2 1661.09  4808.4 1660.02  4841.6 1658.49
  4915.9 1657.50  4958.3 1658.07  4978.1 1657.67  4982.3 1657.15  4994.4 1653.08
  5000.7 1651.88  5000.9 1651.27  5001.1 1650.77  5004.6 1650.77  5004.9 1651.27
  5005.0 1651.89  5006.3 1652.21  5029.7 1657.37  5075.0 1658.28  5096.5 1660.00
  5099.8 1659.76  5118.3 1661.77  5142.1 1662.75  5186.4 1666.52  5211.1 1667.91
#Mann=4,-1,0
  4580.7    0.07       0  5000.9    0.05       0  5004.9    0.07       0
  5142.1   0.035       0
Bank Sta=5000.9,5004.9
Exp/Cntr=0.3,0.1

Type RM Length L Ch R = 1,7252,393,393,393
BEGIN DESCRIPTION:
Stone Creek 16.0
END DESCRIPTION:
XS GIS Cut Line= 3
      1924175.01     13902925.01      1924075.00     13902775.00
      1923775.04     13902475.04
#Sta/Elev= 30
  4815.6 1666.78  4867.3 1662.32  4875.5 1661.71  4881.7 1661.74  4899.3 1659.71
  4916.6 1658.59  4935.8 1655.80  4955.5 1654.52  4979.6 1650.38  4996.7 1649.71
  4997.0 1649.21  5000.5 1649.21  5000.7 1649.71  5009.3 1650.28  5026.3 1650.35
  5043.3 1652.18  5058.7 1651.94  5071.4 1651.65  5085.7 1651.60  5092.0 1652.42
  5157.5 1654.51  5192.5 1656.30  5263.9 1658.36  5299.9 1660.11  5308.4 1660.95
  5324.0 1661.11  5386.2 1664.66  5390.4 1665.24  5407.4 1665.92  5420.1 1667.12
#Mann=6,-1,0
  4815.6    0.07       0  4996.7    0.05       0  5000.7    0.07       0
  5058.7   0.035       0  5071.4    0.07       0  5157.5   0.035       0
Bank Sta=4996.7,5000.7
Exp/Cntr=0.3,0.1

Type RM Length L Ch R = 1,6859,513,513,513
BEGIN DESCRIPTION:
Stone Creek 15.0
END DESCRIPTION:
XS GIS Cut Line= 3
      1924374.99     13902724.97      1924301.55     13902520.59
      1923862.73     13902241.93
#Sta/Elev= 30
  4657.7 1663.52  4680.3 1662.75  4736.6 1657.90  4771.8 1654.04  4839.5 1648.83
  4839.8 1648.33  4843.5 1648.83  4854.3 1650.04  4857.5 1650.77  4860.9 1652.78
  4867.0 1653.41  4872.6 1655.00  4883.5 1655.75  4996.7 1655.08  5050.8 1656.14
  5059.7 1655.38  5068.4 1652.91  5079.2 1652.03  5109.7 1654.93  5185.8 1657.65
  5219.3 1660.73  5256.9 1663.03  5274.7 1665.51  5278.2 1666.62  5303.1 1668.81
  5328.0 1676.20  5342.2 1676.36  5355.3 1678.38  5363.5 1678.61  5394.7 1683.32
#Mann=4,-1,0
  4657.7    0.07       0  4839.5    0.05       0  4843.5    0.07       0
  5059.7   0.035       0
Bank Sta=4839.5,4843.5
Exp/Cntr=0.3,0.1

Type RM Length L Ch R = 1,6346,405,405,405
BEGIN DESCRIPTION:
Stone Creek 14.0
END DESCRIPTION:
XS GIS Cut Line= 4
      1924775.03     13902225.04      1924775.00     13902225.00
      1924575.00     13902125.00      1924275.01     13901925.00
#Sta/Elev= 30
  4782.7 1646.02  4823.0 1645.02  4843.2 1643.34  4857.6 1642.91  4871.0 1641.06
  4874.4 1641.29  4881.9 1640.03  4887.8 1639.93  4897.9 1639.89  4904.6 1638.07
  4921.3 1636.20  4978.0 1636.93  5000.6 1635.92  5000.9 1635.42  5004.4 1635.42
  5004.6 1635.92  5010.0 1636.38  5022.2 1639.92  5030.3 1640.91  5077.2 1641.09
  5098.8 1642.66  5115.2 1642.85  5145.7 1644.58  5163.7 1646.55  5185.4 1646.70
  5192.6 1647.83  5259.0 1652.45  5312.0 1656.37  5350.7 1660.19  5366.9 1660.86
#Mann=6,-1,0
  4782.7    0.07       0  4887.8   0.035       0  5000.6   0.035       0
  5004.6   0.035       0  5259.0    0.07       0  5312.0   0.035       0
Bank Sta=5000.6,5004.6
Exp/Cntr=0.3,0.1

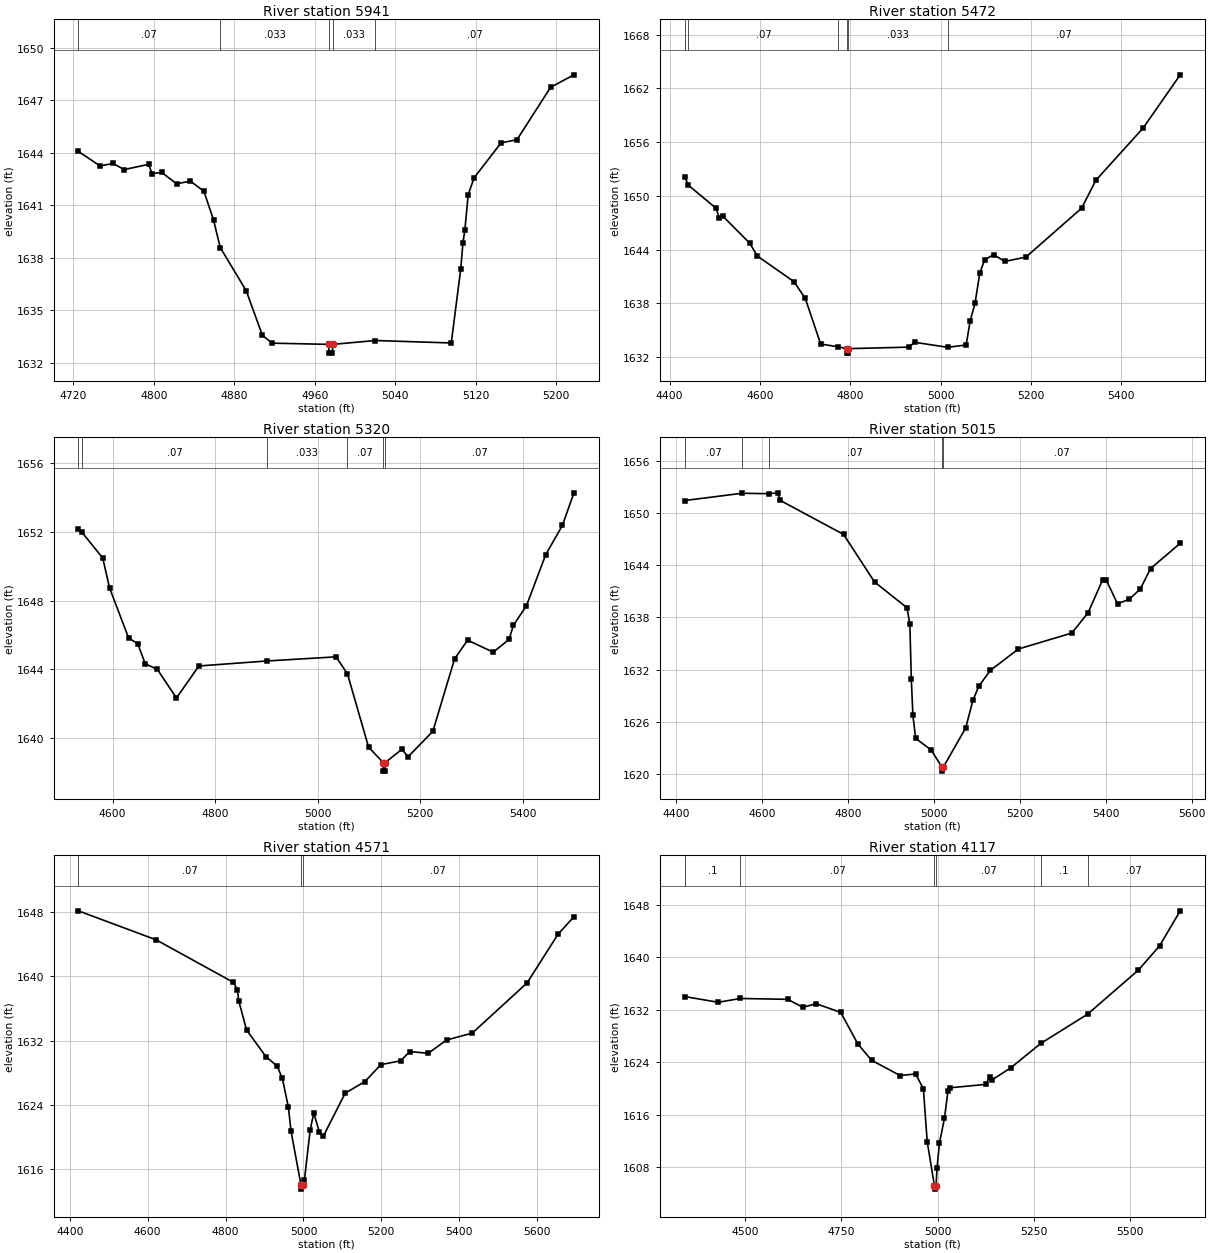
Type RM Length L Ch R = 1,5941,469,469,469
BEGIN DESCRIPTION:
Stone Creek 13.0
END DESCRIPTION:
XS GIS Cut Line= 3
      1924875.00     13902124.99      1924775.00     13901875.00
      1924574.96     13901774.98
#Sta/Elev= 30
  4724.8 1644.08  4746.4 1643.25  4759.3 1643.39  4770.5 1643.04  4794.7 1643.34
  4798.1 1642.81  4807.7 1642.88  4822.5 1642.23  4836.3 1642.38  4849.7 1641.80
  4859.3 1640.16  4865.9 1638.59  4891.8 1636.12  4907.8 1633.58  4917.6 1633.13
  4973.8 1633.06  4974.0 1632.56  4977.5 1632.56  4977.8 1633.06  5020.3 1633.28
  5095.7 1633.14  5105.1 1637.36  5107.3 1638.86  5109.2 1639.58  5112.5 1641.61
  5118.5 1642.58  5145.3 1644.57  5161.0 1644.74  5194.5 1647.74  5217.7 1648.45
#Mann=5,-1,0
  4724.8    0.07       0  4865.9   0.033       0  4973.8   0.033       0
  4977.8   0.033       0  5020.3    0.07       0
Bank Sta=4973.8,4977.8
Exp/Cntr=0.3,0.1

Type RM Length L Ch R = 1,5472,152,152,152
BEGIN DESCRIPTION:
Stone Creek 12.0
END DESCRIPTION:
XS GIS Cut Line= 3
      1925425.01     13901925.01      1925025.00     13901525.00
      1924675.07     13901125.08
#Sta/Elev= 30
  4433.2 1652.16  4441.5 1651.20  4503.2 1648.62  4509.5 1647.59  4518.0 1647.74
  4577.4 1644.73  4594.4 1643.29  4675.0 1640.45  4700.4 1638.57  4734.4 1633.48
  4773.5 1633.16  4791.8 1632.96  4792.0 1632.46  4795.5 1632.46  4795.8 1632.96
  4929.5 1633.13  4942.3 1633.67  5015.6 1633.11  5056.5 1633.37  5065.5 1636.10
  5076.1 1638.01  5086.8 1641.43  5097.5 1642.88  5117.2 1643.45  5142.0 1642.69
  5188.8 1643.18  5312.1 1648.64  5343.6 1651.75  5448.2 1657.58  5530.3 1663.52
#Mann=6,-1,0
  4433.2     0.1       0  4441.5    0.07       0  4773.5   0.033       0
  4791.8   0.033       0  4795.8   0.033       0  5015.6    0.07       0
Bank Sta=4791.8,4795.8
Exp/Cntr=0.3,0.1

Type RM Length L Ch R = 1,5320,305,305,305
BEGIN DESCRIPTION:
Stone Creek 11.1
END DESCRIPTION:
XS GIS Cut Line= 4
      1925457.84     13901900.15      1925297.26     13901730.89
      1925097.61     13901470.47      1924828.52     13901166.67
#Sta/Elev= 30
  4533.1 1652.14  4540.4 1651.96  4580.8 1650.47  4594.0 1648.74  4631.2 1645.83
  4649.1 1645.49  4663.6 1644.33  4687.3 1644.00  4724.6 1642.34  4768.4 1644.20
  4901.1 1644.49  5036.0 1644.73  5058.3 1643.75  5099.6 1639.48  5128.1 1638.59
  5128.4 1638.09  5131.9 1638.09  5132.2 1638.59  5164.7 1639.36  5176.7 1638.92
  5225.1 1640.41  5267.5 1644.62  5292.9 1645.70  5342.8 1645.00  5373.7 1645.74
  5382.2 1646.56  5407.7 1647.70  5445.2 1650.66  5477.9 1652.37  5500.4 1654.26
#Mann=6,-1,0
  4533.1     0.1       0  4540.4    0.07       0  4901.1   0.033       0
  5058.3    0.07       0  5128.1   0.033       0  5132.2    0.07       0
Bank Sta=5128.1,5132.2
Exp/Cntr=0.3,0.1

Type RM Length L Ch R = 1,5015,444,444,444
BEGIN DESCRIPTION:
Stone Creek 11.0
END DESCRIPTION:
XS GIS Cut Line= 5
      1925945.18     13901785.09      1925525.00     13901575.00
      1925425.00     13901525.00      1925175.00     13901325.00
      1924978.09     13901167.47
#Sta/Elev= 30
  4419.5 1651.46  4553.4 1652.30  4615.7 1652.25  4636.6 1652.35  4642.5 1651.47
  4789.7 1647.56  4861.7 1642.09  4937.3 1639.12  4944.0 1637.22  4947.4 1630.86
  4951.1 1626.74  4957.4 1624.08  4993.6 1622.75  5018.2 1620.81  5018.4 1620.31
  5022.3 1620.81  5074.0 1625.28  5090.8 1628.46  5104.8 1630.11  5131.7 1631.92
  5196.7 1634.37  5321.2 1636.21  5358.9 1638.55  5393.1 1642.36  5401.6 1642.26
  5427.5 1639.58  5455.0 1640.10  5480.6 1641.28  5504.3 1643.63  5573.4 1646.54
#Mann=5,-1,0
  4419.5    0.07       0  4553.4     0.1       0  4615.7    0.07       0
  5018.2    0.05       0  5022.3    0.07       0
Bank Sta=5018.2,5022.3
Exp/Cntr=0.3,0.1

Type RM Length L Ch R = 1,4571,454,454,454
BEGIN DESCRIPTION:
Stone Creek 10.0
END DESCRIPTION:
XS GIS Cut Line= 5
      1925981.61     13901738.22      1925775.00     13901325.00
      1925725.00     13901225.00      1925475.00     13901175.00
      1925039.97     13901087.99
#Sta/Elev= 30
  4422.0 1648.17  4621.6 1644.56  4820.3 1639.25  4830.4 1638.33  4833.7 1636.98
  4853.8 1633.33  4903.4 1630.01  4932.4 1628.82  4945.8 1627.29  4961.2 1623.72
  4968.2 1620.68  4993.7 1613.99  4993.9 1613.49  4997.8 1613.99  5002.6 1614.68
  5017.2 1620.86  5026.4 1622.96  5040.8 1620.64  5050.8 1620.07  5107.1 1625.45
  5157.6 1626.89  5198.9 1629.01  5249.7 1629.48  5272.8 1630.64  5320.1 1630.41
  5367.2 1632.07  5433.3 1632.93  5574.0 1639.18  5653.5 1645.25  5694.4 1647.44
#Mann=3,-1,0
  4422.0    0.07       0  4993.7    0.05       0  4997.8    0.07       0
Bank Sta=4993.7,4997.8
Exp/Cntr=0.3,0.1

Type RM Length L Ch R = 1,4117,435,435,435
BEGIN DESCRIPTION:
Stone Creek 9.0
END DESCRIPTION:
XS GIS Cut Line= 5
      1926463.08     13901119.04      1925975.00     13900875.00
      1925875.00     13900825.00      1925775.00     13900825.00
      1925244.39     13900825.00
#Sta/Elev= 30
  4342.5 1634.00  4429.8 1633.12  4487.6 1633.70  4610.9 1633.57  4649.7 1632.35
  4684.7 1632.90  4748.4 1631.57  4792.8 1626.77  4828.5 1624.27  4902.7 1621.95
  4942.9 1622.18  4963.1 1619.94  4973.1 1611.85  4991.9 1605.12  4992.2 1604.62
  4996.1 1605.12  4998.5 1607.78  5004.9 1611.65  5018.0 1615.45  5027.0 1619.58
  5033.0 1620.08  5126.0 1620.60  5135.0 1621.76  5142.0 1621.30  5190.0 1623.11
  5268.3 1626.85  5389.8 1631.30  5522.0 1638.03  5577.0 1641.73  5630.6 1647.07
#Mann=6,-1,0
  4342.5     0.1       0  4487.6    0.07       0  4991.9    0.05       0
  4996.1    0.07       0  5268.3     0.1       0  5389.8    0.07       0
Bank Sta=4991.9,4996.1
Exp/Cntr=0.3,0.1

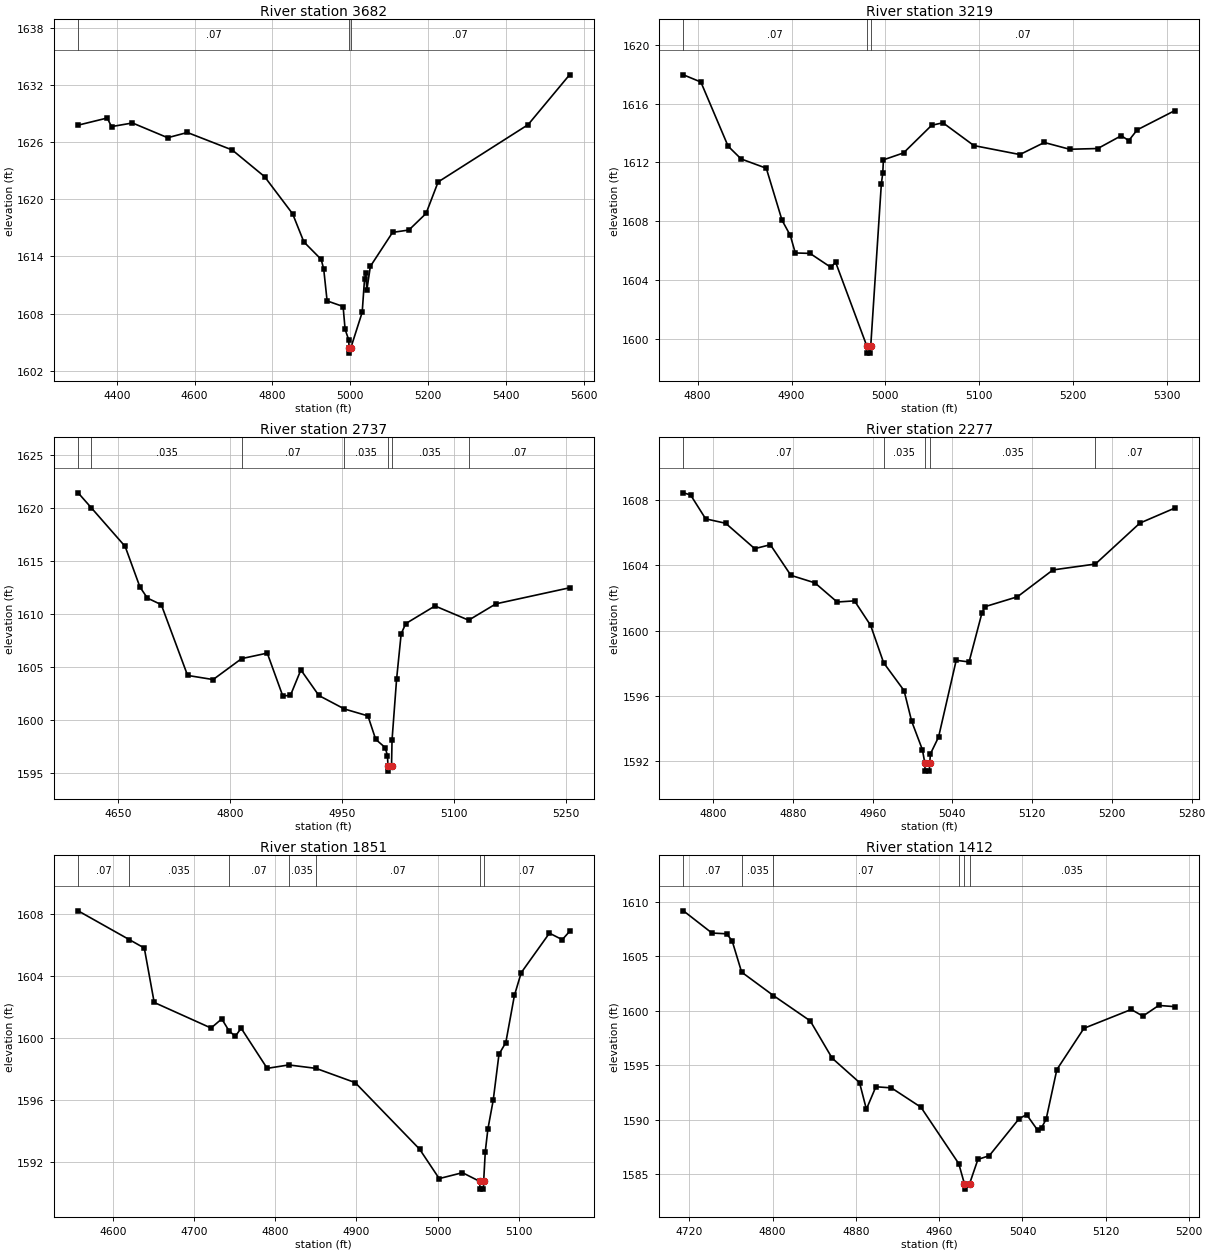
Type RM Length L Ch R = 1,3682,463,463,463
BEGIN DESCRIPTION:
Stone Creek 8.0
END DESCRIPTION:
XS GIS Cut Line= 5
      1926660.40     13900865.26      1926225.00     13900575.00
      1926075.00     13900475.00      1925825.00     13900475.00
      1925516.56     13900475.00
#Sta/Elev= 30
  4300.9 1627.80  4375.6 1628.55  4386.7 1627.65  4440.5 1628.03  4530.9 1626.48
  4581.4 1627.03  4696.7 1625.19  4779.7 1622.39  4851.8 1618.48  4880.6 1615.53
  4925.1 1613.69  4931.6 1612.67  4940.3 1609.33  4981.4 1608.74  4986.5 1606.34
  4996.0 1605.21  4996.5 1604.34  4996.8 1603.84  5000.8 1604.34  5030.4 1608.13
  5036.4 1611.60  5039.4 1612.21  5042.4 1610.50  5051.4 1612.96  5108.4 1616.53
  5150.4 1616.78  5194.4 1618.52  5225.4 1621.83  5456.4 1627.85  5562.9 1633.09
#Mann=3,-1,0
  4300.9    0.07       0  4996.5    0.05       0  5000.8    0.07       0
Bank Sta=4996.5,5000.8
Exp/Cntr=0.3,0.1

Type RM Length L Ch R = 1,3219,482,482,482
BEGIN DESCRIPTION:
Stone Creek 7.0
END DESCRIPTION:
XS GIS Cut Line= 3
      1926474.98     13900374.96      1926375.00     13900175.00
      1926074.97     13900175.00
#Sta/Elev= 30
  4784.8 1617.96  4803.4 1617.47  4832.4 1613.11  4846.3 1612.24  4873.1 1611.61
  4889.9 1608.07  4898.7 1607.04  4904.0 1605.85  4919.7 1605.82  4942.0 1604.87
  4946.9 1605.23  4980.1 1599.54  4980.4 1599.04  4984.1 1599.04  4984.4 1599.54
  4995.7 1610.56  4997.2 1611.28  4997.9 1612.18  5019.3 1612.65  5049.3 1614.53
  5061.3 1614.70  5094.3 1613.15  5143.3 1612.54  5169.3 1613.36  5196.3 1612.90
  5226.3 1612.95  5251.3 1613.82  5259.3 1613.49  5268.3 1614.22  5308.4 1615.53
#Mann=3,-1,0
  4784.8    0.07       0  4980.1    0.05       0  4984.4    0.07       0
Bank Sta=4980.1,4984.4
Exp/Cntr=0.3,0.1

Type RM Length L Ch R = 1,2737,460,460,460
BEGIN DESCRIPTION:
Stone Creek 6.0
END DESCRIPTION:
XS GIS Cut Line= 3
      1926875.00     13900075.00      1926525.00     13899875.00
      1926274.97     13899824.99
#Sta/Elev= 30
  4596.4 1621.40  4614.2 1619.98  4659.4 1616.35  4679.2 1612.53  4689.2 1611.49
  4707.8 1610.87  4743.0 1604.21  4777.2 1603.82  4815.3 1605.79  4849.7 1606.31
  4870.5 1602.27  4880.8 1602.34  4894.7 1604.73  4918.8 1602.32  4953.0 1601.05
  4984.5 1600.40  4994.9 1598.19  5007.6 1597.42  5010.7 1596.65  5011.3 1595.70
  5011.7 1595.20  5016.1 1595.70  5016.8 1598.14  5022.9 1603.87  5029.0 1608.13
  5035.2 1609.09  5074.3 1610.75  5119.4 1609.41  5155.9 1610.95  5254.5 1612.46
#Mann=7,-1,0
  4596.4    0.07       0  4614.2   0.035       0  4815.3    0.07       0
  4953.0   0.035       0  5011.3   0.035       0  5016.1   0.035       0
  5119.4    0.07       0
Bank Sta=5011.3,5016.1
Exp/Cntr=0.3,0.1

Type RM Length L Ch R = 1,2277,426,426,426
BEGIN DESCRIPTION:
Stone Creek 5.0
END DESCRIPTION:
XS GIS Cut Line= 3
      1926924.99     13899574.99      1926725.00     13899475.00
      1926474.96     13899575.02
#Sta/Elev= 30
  4770.2 1608.41  4777.4 1608.28  4792.5 1606.82  4812.6 1606.55  4841.7 1605.00
  4857.4 1605.24  4878.0 1603.37  4902.1 1602.91  4924.4 1601.74  4941.8 1601.81
  4958.0 1600.31  4971.0 1598.03  4991.5 1596.33  4999.1 1594.46  5009.9 1592.72
  5012.3 1591.91  5012.6 1591.41  5016.8 1591.41  5017.2 1591.91  5018.0 1592.47
  5026.1 1593.49  5043.8 1598.18  5056.7 1598.08  5069.7 1601.09  5072.9 1601.46
  5105.2 1602.06  5140.8 1603.70  5183.4 1604.06  5228.0 1606.56  5263.1 1607.48
#Mann=5,-1,0
  4770.2    0.07       0  4971.0   0.035       0  5012.3   0.035       0
  5017.2   0.035       0  5183.4    0.07       0
Bank Sta=5012.3,5017.2
Exp/Cntr=0.3,0.1

Type RM Length L Ch R = 1,1851,439,439,439
BEGIN DESCRIPTION:
Stone Creek 4.0
END DESCRIPTION:
XS GIS Cut Line= 3
      1927068.37     13899187.94      1926625.00     13899125.00
      1926475.03     13899075.01
#Sta/Elev= 30
  4556.8 1608.18  4620.0 1606.32  4638.4 1605.78  4650.6 1602.27  4720.7 1600.62
  4733.9 1601.21  4742.6 1600.46  4750.5 1600.08  4757.8 1600.61  4789.9 1598.02
  4816.5 1598.24  4850.0 1598.02  4898.4 1597.10  4977.8 1592.81  5002.0 1590.91
  5030.7 1591.29  5051.9 1590.73  5052.3 1590.23  5056.5 1590.23  5056.8 1590.73
  5058.8 1592.65  5062.0 1594.10  5068.6 1595.97  5075.7 1598.93  5084.1 1599.68
  5094.7 1602.72  5103.1 1604.19  5137.9 1606.74  5153.7 1606.32  5162.7 1606.85
#Mann=7,-1,0
  4556.8    0.07       0  4620.0   0.035       0  4742.6    0.07       0
  4816.5   0.035       0  4850.0    0.07       0  5051.9    0.05       0
  5056.8    0.07       0
Bank Sta=5051.9,5056.8
Exp/Cntr=0.3,0.1

Type RM Length L Ch R = 1,1412,428,428,428
BEGIN DESCRIPTION:
Stone Creek 3.0
END DESCRIPTION:
XS GIS Cut Line= 3
      1927125.03     13899025.02      1926875.00     13898875.00
      1926774.98     13898724.97
#Sta/Elev= 30
  4714.4 1609.19  4741.8 1607.15  4755.8 1607.08  4761.1 1606.46  4770.3 1603.56
  4800.8 1601.41  4836.2 1599.08  4857.2 1595.66  4883.5 1593.42  4890.1 1590.97
  4899.2 1593.03  4914.1 1592.93  4942.5 1591.15  4978.8 1585.97  4984.2 1584.13
  4984.6 1583.63  4989.2 1584.13  4997.2 1586.36  5008.1 1586.70  5036.6 1590.08
  5043.9 1590.48  5054.7 1589.02  5058.3 1589.27  5062.7 1590.05  5073.0 1594.61
  5099.0 1598.40  5144.4 1600.13  5155.6 1599.52  5170.8 1600.50  5186.3 1600.39
#Mann=6,-1,0
  4714.4    0.07       0  4770.3   0.035       0  4800.8    0.07       0
  4978.8   0.035       0  4984.2   0.035       0  4989.2   0.035       0
Bank Sta=4984.2,4989.2
Exp/Cntr=0.3,0.1

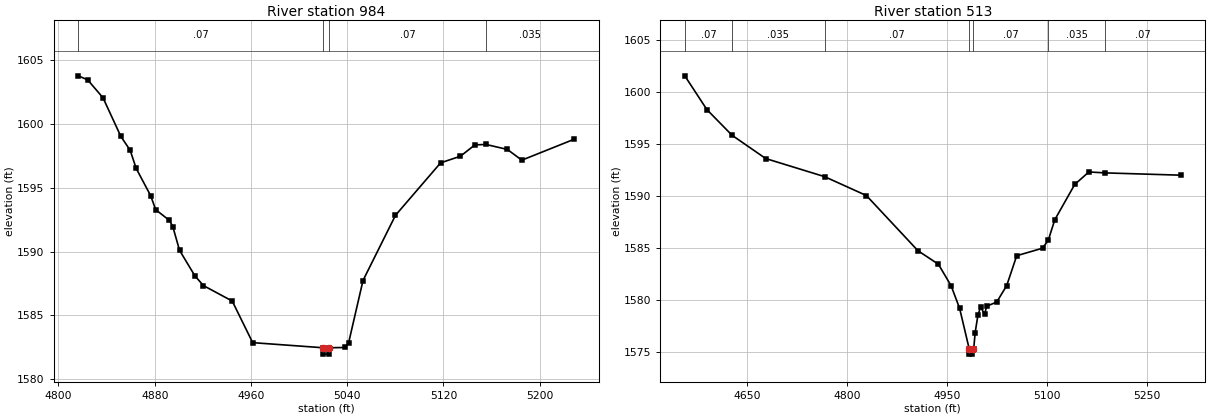
Type RM Length L Ch R = 1,984,471,471,471
BEGIN DESCRIPTION:
Stone Creek 2.0
END DESCRIPTION:
XS GIS Cut Line= 3
      1927225.02     13898725.02      1927075.00     13898575.00
      1926875.06     13898575.00
#Sta/Elev= 30
  4816.5 1603.78  4824.3 1603.46  4837.0 1602.06  4851.8 1599.04  4859.6 1597.94
  4864.6 1596.52  4876.6 1594.39  4880.8 1593.29  4892.2 1592.45  4895.0 1591.97
  4900.6 1590.11  4913.4 1588.10  4920.5 1587.34  4944.4 1586.13  4961.4 1582.87
  5019.8 1582.47  5020.2 1581.97  5024.5 1581.97  5024.8 1582.47  5038.1 1582.49
  5041.1 1582.84  5053.1 1587.74  5080.1 1592.85  5117.6 1596.96  5134.1 1597.48
  5146.1 1598.37  5155.4 1598.40  5173.1 1598.01  5185.1 1597.17  5228.6 1598.81
#Mann=4,-1,0
  4816.5    0.07       0  5019.8    0.05       0  5024.8    0.07       0
  5155.4   0.035       0
Bank Sta=5019.8,5024.8
Exp/Cntr=0.3,0.1

Type RM Length L Ch R = 1,513,0,0,0
BEGIN DESCRIPTION:
Stone Creek 1.0
END DESCRIPTION:
XS GIS Cut Line= 3
      1927542.52     13898485.50      1927225.00     13898175.00
      1926925.19     13898148.29
#Sta/Elev= 30
  4555.9 1601.55  4589.1 1598.30  4626.9 1595.83  4677.5 1593.59  4765.9 1591.85
  4828.8 1590.03  4906.3 1584.72  4937.0 1583.42  4956.1 1581.35  4968.9 1579.17
  4983.3 1575.27  4983.7 1574.77  4988.0 1574.77  4988.3 1575.27  4990.1 1575.29
  4992.2 1576.83  4996.4 1578.53  5000.5 1579.31  5006.4 1578.59  5009.5 1579.38
  5024.6 1579.78  5039.6 1581.36  5054.7 1584.24  5093.8 1584.97  5102.4 1585.79
  5111.9 1587.70  5141.9 1591.10  5163.1 1592.30  5187.4 1592.21  5301.0 1591.99
#Mann=7,-1,0
  4555.9    0.07       0  4626.9   0.035       0  4765.9    0.07       0
  4983.3    0.05       0  4988.3    0.07       0  5102.4   0.035       0
  5187.4    0.07       0
Bank Sta=4983.3,4988.3
Exp/Cntr=0.3,0.1

Chan Stop Cuts=-1