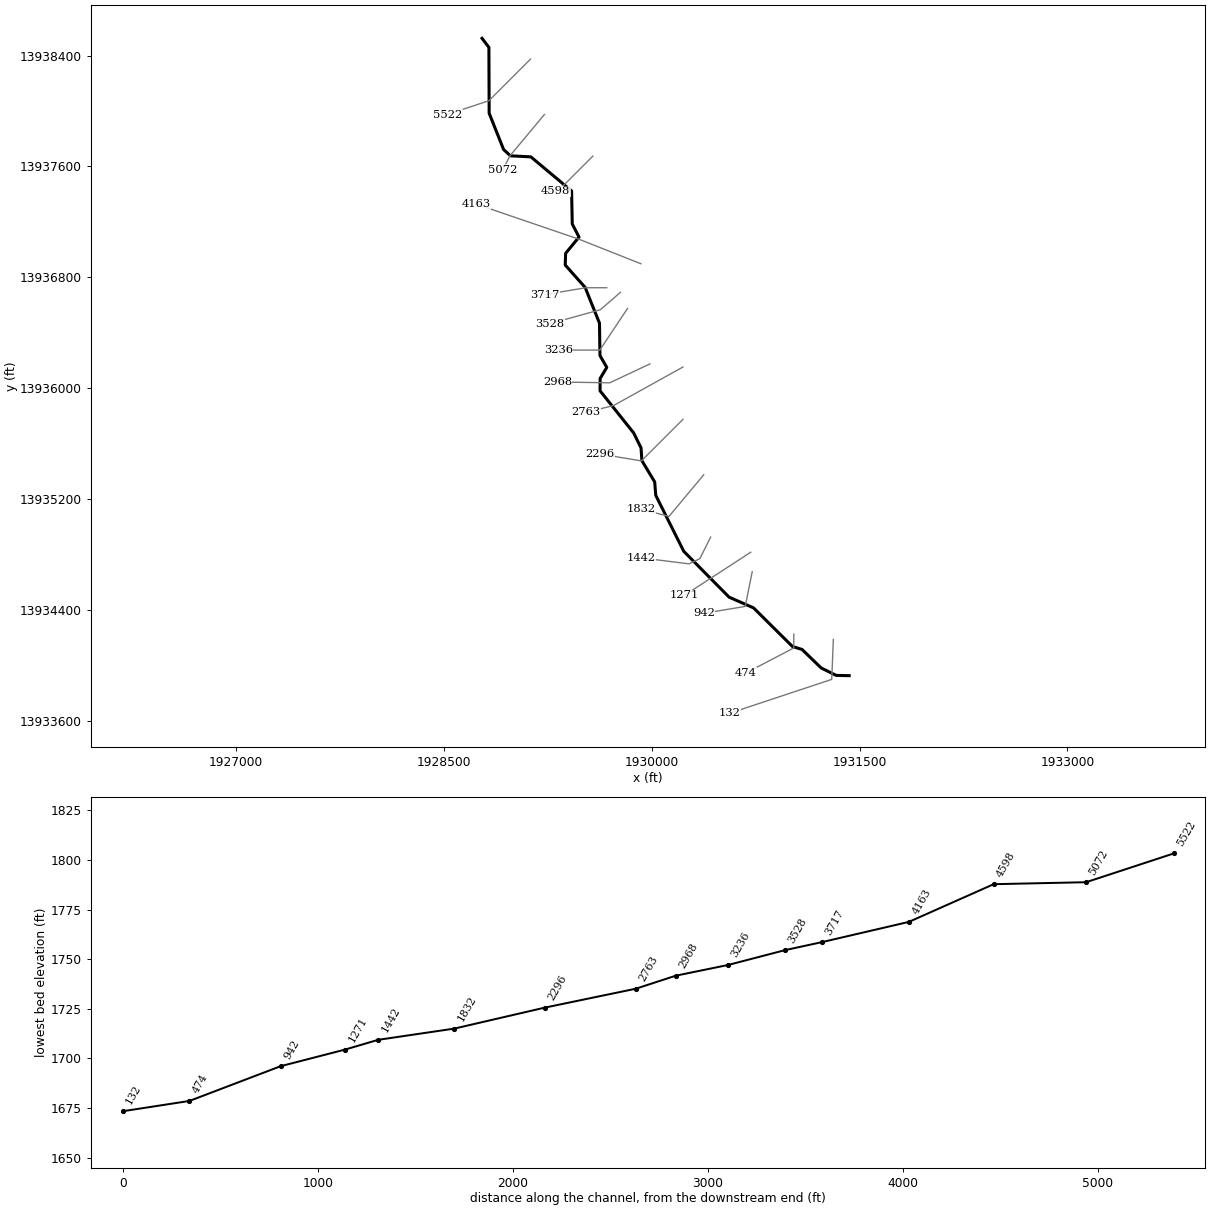
--- Stream QC-1.prj (project) ---

Proj Title=Stream QC-1 Base Level Engineering
Current Plan=p01
Default Exp/Contr=0.3,0.1
English Units
Geom File=g01
Flow File=f01
Plan File=p01
Y Axis Title=Elevation
X Axis Title(PF)=Main Channel Distance
X Axis Title(XS)=Station
BEGIN DESCRIPTION:
Stream QC-1
END DESCRIPTION:
DSS Export Rating Curves= 0
DSS Export Rating Curve Sorted= 0
DSS Export Volume Flow Curves= 0
DXF OffsetX= 0
DXF OffsetY= 0
DXF ScaleX= 1
DXF ScaleY= 10

--- Stream QC-1.p01 (plan) ---

Plan Title=Multiple Run
Short Identifier=Multiple
Geom File=g01
Flow File=f01
Subcritical Flow
K Sum by GR= 0
Std Step Tol= 0.01
Critical Tol= 0.01
Num of Std Step Trials= 20
Max Error Tol= 0.3
Flow Tol Ratio= 0.001
Split Flow NTrial= 30
Split Flow Tol= 0.02
Split Flow Ratio= 0.02
Log Output Level= 0
Friction Slope Method= 1
Unsteady Friction Slope Method= 2
Unsteady Bridges Friction Slope Method= 1
Parabolic Critical Depth
Global Vel Dist=  1 , 1 , 1
Global Log Level= 0
CheckData=True
Encroach Param= -1, 0, 0, 0
BEGIN DESCRIPTION:
Multiple Run
END DESCRIPTION:

--- Stream QC-1.f01 (steady flow) ---

Flow Title=Multiple
Program Version=4.10
Number of Profiles= 7
Profile Names=10-year,25-year,50-year,1pct_min,100-year,1pct_plu,500-year
River Rch & RM=Stream QC-1,Reach-1         ,5522
     701    1163    1594    1059    2113    4215    3657
Boundary for River Rch & Prof#=Stream QC-1,Reach-1         , 1
Up Type= 0
Dn Type= 3
Dn Slope=0.005
Boundary for River Rch & Prof#=Stream QC-1,Reach-1         , 2
Up Type= 0
Dn Type= 3
Dn Slope=0.005
Boundary for River Rch & Prof#=Stream QC-1,Reach-1         , 3
Up Type= 0
Dn Type= 3
Dn Slope=0.005
Boundary for River Rch & Prof#=Stream QC-1,Reach-1         , 4
Up Type= 0
Dn Type= 3
Dn Slope=0.005
Boundary for River Rch & Prof#=Stream QC-1,Reach-1         , 5
Up Type= 0
Dn Type= 3
Dn Slope=0.005
Boundary for River Rch & Prof#=Stream QC-1,Reach-1         , 6
Up Type= 0
Dn Type= 3
Dn Slope=0.005
Boundary for River Rch & Prof#=Stream QC-1,Reach-1         , 7
Up Type= 0
Dn Type= 3
Dn Slope=0.005
DSS Import GetInterval= 0
DSS Import GetPeak= 0
DSS Import FillOption= 0

--- Stream QC-1.g01 (geometry) ---

Geom Title=Existing Conditions
Program Version=4.10

River Reach=Stream QC-1     ,Reach-1
Reach XY= 30
        1928775.       13938525.      1928824.64     13938459.85
      1928826.38     13937984.66      1928930.71     13937722.41
      1928980.26      13937677.1      1929127.45     13937669.53
      1929421.47     13937423.55      1929426.24      13937185.5
      1929475.04     13937090.34      1929378.47      13936973.5
       1929375.4     13936888.92      1929519.17      13936727.3
      1929622.62     13936469.47      1929626.24      13936235.5
       1929675.4       13936150.      1929627.31     13936069.44
      1929626.96     13935980.89      1929869.16     13935677.29
      1929922.56     13935569.44      1929928.83     13935476.58
      1930021.17     13935323.42      1930028.83     13935226.58
      1930230.83      13934822.7      1930558.32     13934491.64
      1930734.68     13934414.24      1931015.32     13934135.78
      1931084.68     13934114.22       1931222.7     13933980.83
      1931330.86     13933927.07        1931425.       13933925.

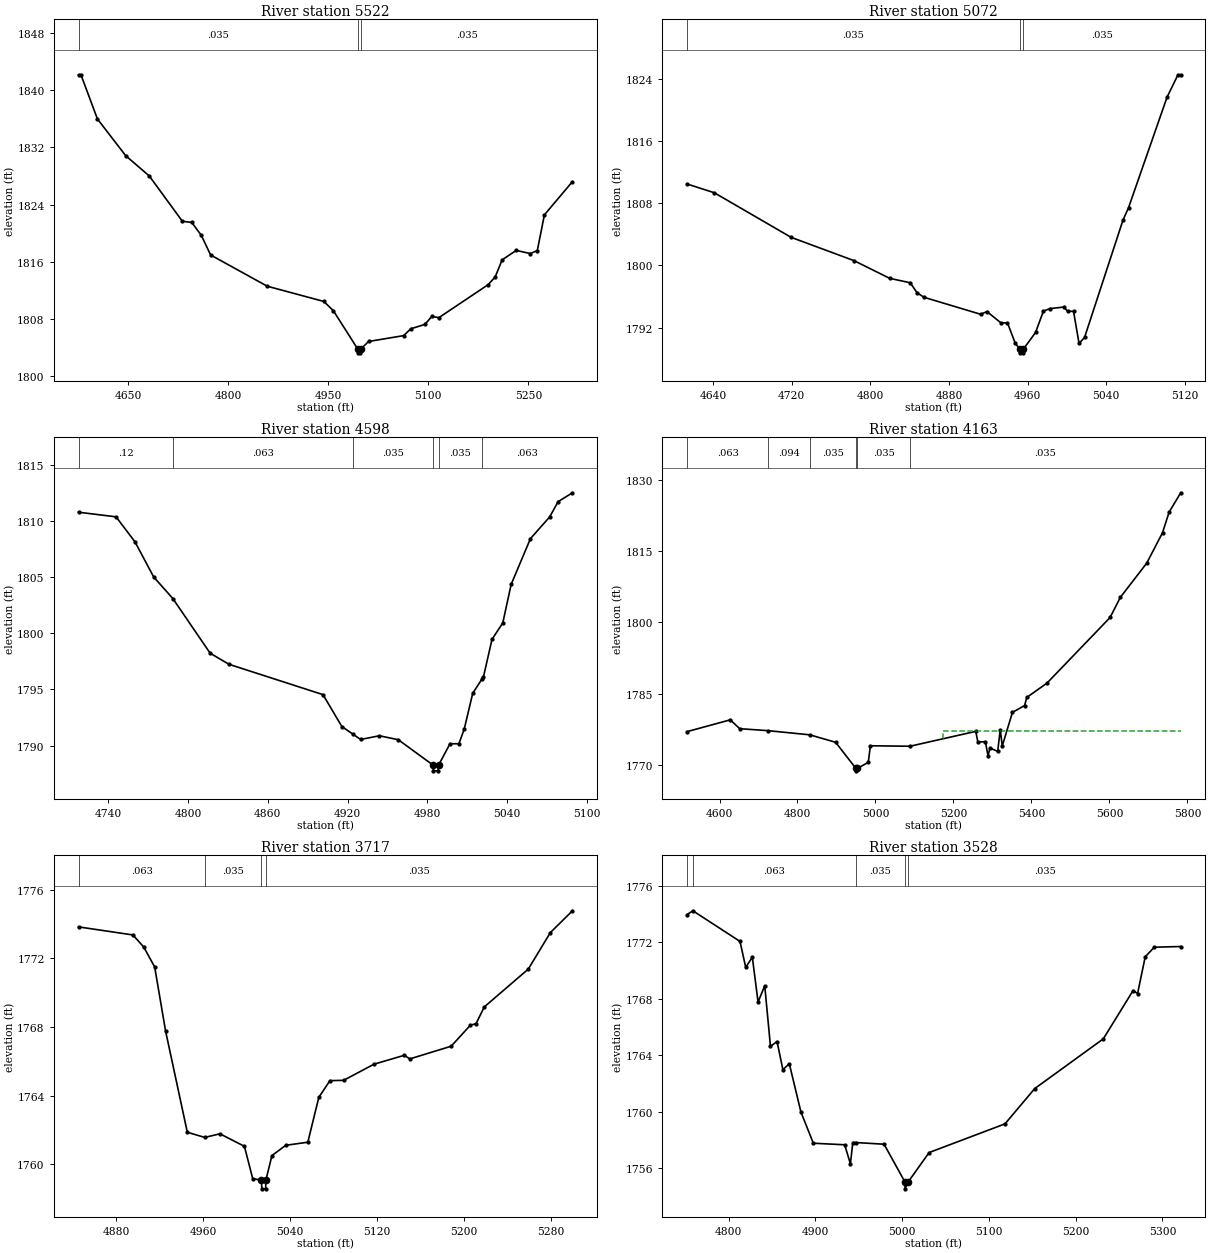
Type RM Length L Ch R = 1 ,5522    ,450,450,450
BEGIN DESCRIPTION:
Stream QC-1 12.0
END DESCRIPTION:
XS GIS Cut Line= 3
      1929125.02     13938375.02        1928825.       13938075.
      1928525.02     13937975.01
#Sta/Elev= 30
  4575.6 1842.17  4579.2 1842.17  4603.9 1835.99  4646.3 1830.85  4681.7 1828.01
  4731.2 1821.68  4745.3 1821.51  4759.5 1819.73  4773.6 1816.96  4858.5 1812.59
  4943.3 1810.46  4957.5 1809.18  4994.4 1803.77  4994.6 1803.27  4998.1 1803.27
  4998.4 1803.77  5010.4 1804.86  5063.1 1805.68  5073.7 1806.64  5094.8 1807.24
  5105.3 1808.37  5115.8 1808.19  5189.6  1812.8  5200.2 1813.88  5210.7 1816.28
  5231.8  1817.6  5252.9 1817.16  5263.4 1817.58    5274 1822.57  5316.1 1827.23
#Mann= 3 ,-1 , 0
  4575.6    .035       0  4994.4    .035       0  4998.4    .035       0
Bank Sta=4994.4,4998.4
XS Rating Curve= 0 ,0
Exp/Cntr=0.3,0.1

Type RM Length L Ch R = 1 ,5072    ,474,474,474
BEGIN DESCRIPTION:
Stream QC-1 11.0
END DESCRIPTION:
XS GIS Cut Line= 3
      1929225.02     13937975.02        1928975.       13937675.
      1928925.02     13937575.04
#Sta/Elev= 30
  4613.4 1810.48  4641.4 1809.34  4719.5 1803.61  4783.3 1800.62  4819.7 1798.34
  4840.6 1797.77  4847.7 1796.46  4854.9 1795.89  4912.2 1793.72  4918.7 1794.06
    4933  1792.6  4939.5 1792.62  4947.3 1790.03  4951.8 1789.26  4952.1 1788.76
  4955.6 1788.76  4955.8 1789.26  4968.1 1791.38    4976 1794.11  4982.5 1794.44
  4996.8 1794.65  5000.7  1794.1  5006.7  1794.1  5012.3 1789.97  5017.9 1790.74
    5057 1805.83  5062.6 1807.41  5101.8 1821.63  5112.9 1824.51  5115.7 1824.51
#Mann= 3 ,-1 , 0
  4613.4    .035       0  4951.8    .035       0  4955.8    .035       0
Bank Sta=4951.8,4955.8
XS Rating Curve= 0 ,0
Exp/Cntr=0.3,0.1

Type RM Length L Ch R = 1 ,4598    ,435,435,435
BEGIN DESCRIPTION:
Stream QC-1 10.0
END DESCRIPTION:
XS GIS Cut Line= 3
      1929574.97     13937674.97        1929375.       13937475.
      1929305.16     13937420.49
#Sta/Elev= 30
  4717.7 1810.77  4745.9 1810.36  4760.1 1808.14  4774.2 1805.01  4788.6 1803.09
  4816.7 1798.22  4830.8 1797.24  4901.5 1794.54  4915.7  1791.7  4923.7 1791.05
  4929.8 1790.55  4943.9 1790.88  4958.1 1790.53  4984.4 1788.26  4984.6 1787.76
  4988.1 1787.76  4988.4 1788.26    4997 1790.17  5003.7 1790.17  5007.7 1791.47
  5014.1 1794.66    5021 1795.92  5022.2 1796.14  5028.6 1799.46  5036.7 1800.92
    5043 1804.35  5057.5 1808.42    5072 1810.36  5078.3 1811.71  5089.1  1812.5
#Mann= 6 ,-1 , 0
  4717.7     .12       0  4788.6    .063       0  4923.7    .035       0
  4984.4    .035       0  4988.4    .035       0    5021    .063       0
Bank Sta=4984.4,4988.4
XS Rating Curve= 0 ,0
Exp/Cntr=0.3,0.1

Type RM Length L Ch R = 1 ,4163    ,446,446,446
BEGIN DESCRIPTION:
Stream QC-1 9.0
END DESCRIPTION:
XS GIS Cut Line= 3
      1929921.57      13936898.1        1929475.       13937075.
      1928730.77     13937329.28
#Sta/Elev= 30
  4516.1 1776.99  4627.6 1779.48  4651.9 1777.62  4725.5  1777.2  4831.5 1776.33
  4897.8 1774.76  4949.9 1769.26  4950.1 1768.76  4953.9 1769.26  4981.6 1770.56
  4986.9 1774.03  5088.6 1773.93  5257.3 1777.06  5262.6 1774.81  5281.8 1774.89
  5288.6 1771.98  5293.9 1773.53  5313.5 1772.86    5320 1777.42  5325.2 1773.99
  5351.3 1781.05  5382.6 1782.49  5387.9 1784.18  5439.9  1787.2  5601.8    1801
  5627.8  1805.2  5695.8 1812.43  5736.2 1818.81  5753.1 1823.14  5782.9 1827.21
#Mann= 6 ,-1 , 0
  4516.1    .063       0  4725.5    .094       0  4831.5    .035       0
  4949.9    .035       0  4953.9    .035       0  5088.6    .035       0
#XS Ineff= 2 , 0
                          5172.2         1777.13
Permanent Ineff=
       F       F
Bank Sta=4949.9,4953.9
XS Rating Curve= 0 ,0
Exp/Cntr=0.3,0.1

Type RM Length L Ch R = 1 ,3717    ,189,189,189
BEGIN DESCRIPTION:
Stream QC-1 8.0
END DESCRIPTION:
XS GIS Cut Line= 3
      1929674.96       13936725.        1929525.       13936725.
        1929225.       13936675.
#Sta/Elev= 30
  4845.6 1773.84  4895.6 1773.37  4905.6 1772.66  4915.6  1771.5  4925.6 1767.77
  4945.6 1761.86  4961.6 1761.56  4975.6 1761.77  4998.1 1761.04  5005.7 1759.16
  5013.8 1759.06  5014.1 1758.56  5017.6 1758.56  5017.8 1759.06  5023.4  1760.5
  5036.1  1761.1  5056.4 1761.28  5066.5  1763.9  5076.7 1764.87  5089.3 1764.89
  5117.2 1765.83  5145.1 1766.35  5150.2 1766.14  5188.2 1766.88  5205.9 1768.11
    5211 1768.19  5218.6 1769.17  5259.1 1771.38  5279.4 1773.51  5299.7 1774.78
#Mann= 4 ,-1 , 0
  4845.6    .063       0  4961.6    .035       0  5013.8    .035       0
  5017.8    .035       0
Bank Sta=5013.8,5017.8
XS Rating Curve= 0 ,0
Exp/Cntr=0.3,0.1

Type RM Length L Ch R = 1 ,3528    ,292,292,292
BEGIN DESCRIPTION:
Mapping XS 7f0f3a0c
END DESCRIPTION:
XS GIS Cut Line= 3
      1929774.26     13936691.91      1929629.24     13936566.38
       1929265.6     13936465.77
#Sta/Elev= 30
  4751.9 1773.94  4758.9 1774.22  4813.2 1772.05  4819.8 1770.21  4827.4 1770.94
    4834 1767.76  4841.7 1768.91  4848.3 1764.62  4855.9 1764.96  4862.6 1762.97
    4870 1763.39  4883.4 1759.97  4897.7 1757.76  4933.8 1757.65  4940.4  1756.3
  4943.2 1757.81  4946.3 1757.81  4979.2 1757.69  5003.1 1755.03  5003.4 1754.53
  5007.1 1755.03  5031.1  1757.1  5118.5 1759.13  5152.8 1761.63  5231.8 1765.15
  5266.1 1768.57  5271.3 1768.36  5280.1 1770.96  5290.5 1771.64    5321 1771.69
#Mann= 5 ,-1 , 0
  4751.9    .035       0  4758.9    .063       0  4946.3    .035       0
  5003.1    .035       0  5007.1    .035       0
Bank Sta=5003.1,5007.1
XS Rating Curve= 0 ,0
Exp/Cntr=0.3,0.1

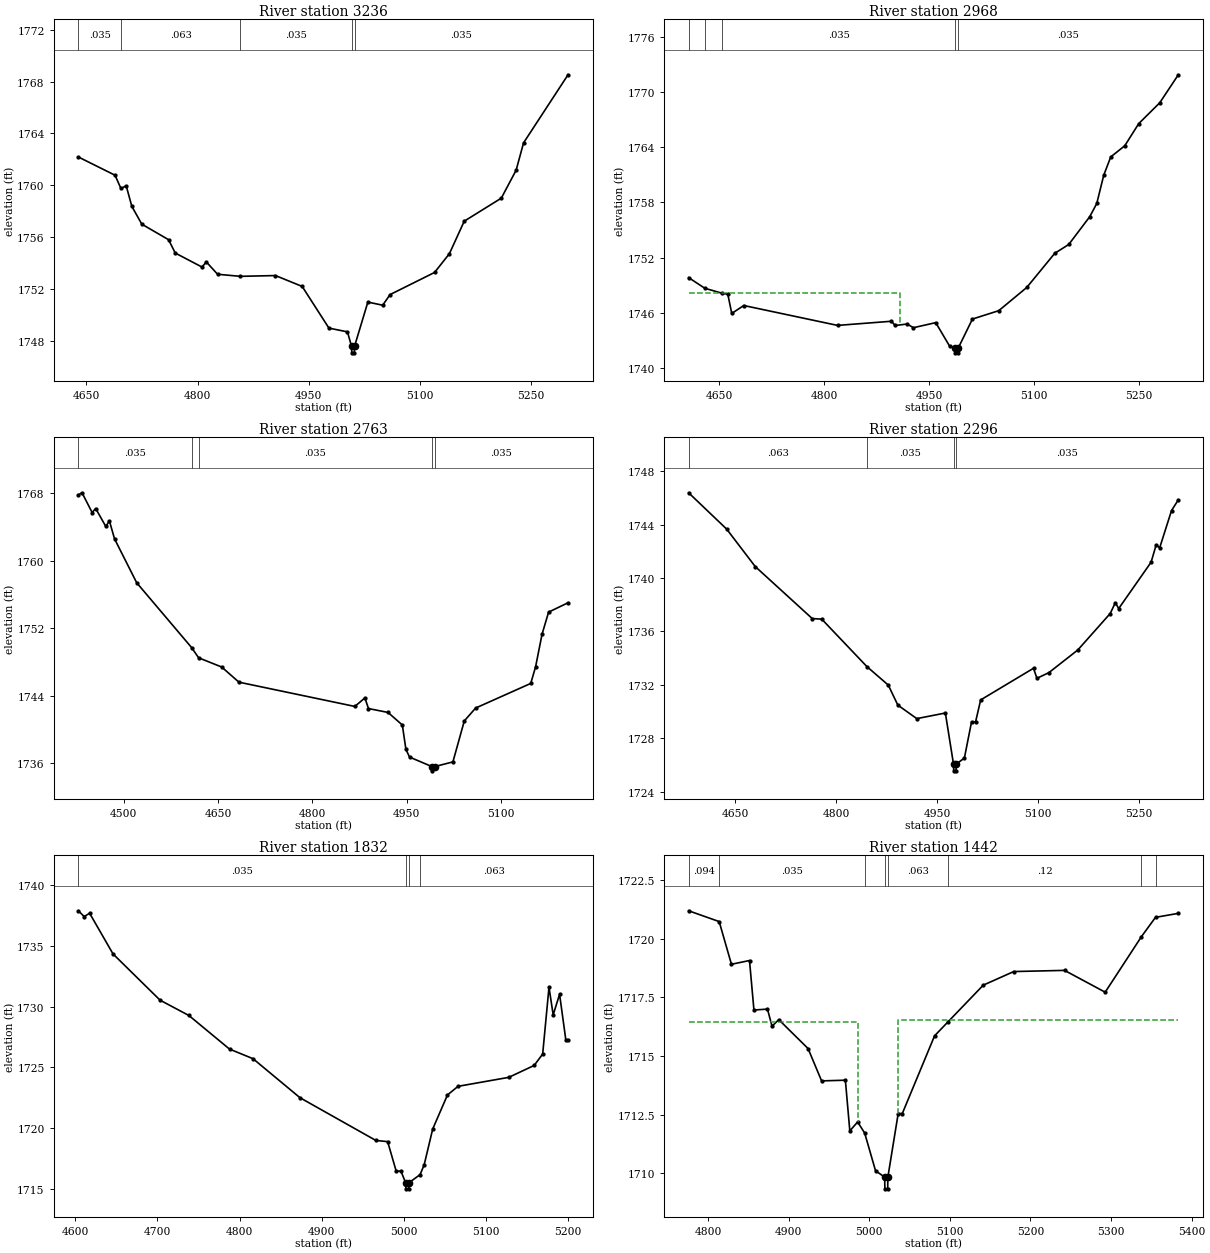
Type RM Length L Ch R = 1 ,3236    ,268,268,268
BEGIN DESCRIPTION:
Stream QC-1 7.0
END DESCRIPTION:
XS GIS Cut Line= 3
      1929824.98     13936574.97        1929625.       13936275.
      1929325.02       13936275.
#Sta/Elev= 30
  4639.1 1762.18  4688.6 1760.77  4696.5 1759.75  4703.7 1759.95  4711.2 1758.37
  4724.7 1756.99  4760.8 1755.79  4769.8 1754.76  4805.8 1753.68  4811.8 1754.07
  4826.9 1753.12  4857.6 1752.96    4905 1753.02    4941 1752.18  4977.1 1748.96
  5002.1 1748.67  5007.6 1747.55  5007.9 1747.05  5011.4 1747.05  5011.6 1747.55
  5029.6 1750.97  5049.6 1750.73  5059.6 1751.55  5119.6 1753.26  5139.6 1754.71
  5159.6 1757.22  5209.6    1759  5229.6 1761.16  5239.6 1763.27  5299.6 1768.53
#Mann= 5 ,-1 , 0
  4639.1    .035       0  4696.5    .063       0  4857.6    .035       0
  5007.6    .035       0  5011.6    .035       0
Bank Sta=5007.6,5011.6
XS Rating Curve= 0 ,0
Exp/Cntr=0.3,0.1

Type RM Length L Ch R = 1 ,2968    ,205,205,205
BEGIN DESCRIPTION:
Mapping XS 9a5f8d4f
END DESCRIPTION:
XS GIS Cut Line= 3
      1929987.45     13936175.37      1929696.84     13936038.72
      1929318.53     13936044.65
#Sta/Elev= 30
  4606.3 1749.83  4629.5 1748.67  4654.3 1748.13  4662.3 1748.02  4667.9 1745.94
  4685.1  1746.8    4819 1744.64  4895.9 1745.09  4901.4 1744.63  4918.4 1744.79
  4927.4 1744.39  4959.3 1744.94  4979.3 1742.36  4987.3 1742.16  4987.5 1741.66
    4991 1741.66  4991.3 1742.16  5011.7 1745.33  5049.3 1746.24  5089.3 1748.76
  5129.3 1752.47  5149.3 1753.43  5179.3 1756.45  5189.3 1757.88  5199.3 1760.96
  5209.3 1762.94  5229.3 1764.15  5249.3 1766.56  5279.3 1768.82  5305.8 1771.86
#Mann= 5 ,-1 , 0
  4606.3    .035       0  4629.5    .063       0  4654.3    .035       0
  4987.3    .035       0  4991.3    .035       0
#XS Ineff= 2 , 0
         4907.62  1748.2
Permanent Ineff=
       F       F
Bank Sta=4987.3,4991.3
XS Rating Curve= 0 ,0
Exp/Cntr=0.3,0.1

Type RM Length L Ch R = 1 ,2763    ,467,467,467
BEGIN DESCRIPTION:
Stream QC-1 6.0
END DESCRIPTION:
XS GIS Cut Line= 3
      1930225.27      13936152.8        1929725.       13935875.
      1929524.98     13935824.99
#Sta/Elev= 30
    4428 1767.83  4433.9 1768.08  4449.9 1765.74  4455.6 1766.21  4471.6 1764.09
  4477.4 1764.74  4485.5 1762.62  4520.8  1757.4  4608.2  1749.7  4619.2  1748.5
  4655.8 1747.41  4683.3 1745.61  4867.5 1742.73  4883.5 1743.74  4889.2 1742.48
  4920.2 1742.02    4943 1740.53  4948.7 1737.64  4954.5 1736.72  4990.2 1735.59
  4990.5 1735.09  4994.2 1735.59  5023.4 1736.15  5041.5 1741.01  5059.5 1742.54
  5147.1 1745.46  5154.8 1747.42  5165.1  1751.3  5175.5 1753.92  5206.4 1755.03
#Mann= 5 ,-1 , 0
    4428    .035       0  4608.2    .063       0  4619.2    .035       0
  4990.2    .035       0  4994.2    .035       0
Bank Sta=4990.2,4994.2
XS Rating Curve= 0 ,0
Exp/Cntr=0.3,0.1

Type RM Length L Ch R = 1 ,2296    ,464,464,464
BEGIN DESCRIPTION:
Stream QC-1 5.0
END DESCRIPTION:
XS GIS Cut Line= 3
      1930225.02     13935775.02        1929925.       13935475.
      1929625.03     13935524.99
#Sta/Elev= 30
  4580.3 1746.38  4636.9 1743.66  4679.3 1740.86  4764.2 1736.96  4778.3 1736.92
  4845.4 1733.37  4877.3 1731.98  4891.5 1730.48  4919.7 1729.47  4962.2 1729.89
  4974.3 1726.06  4974.6 1725.56  4978.1 1725.56  4978.3 1726.06  4990.5 1726.52
  5001.1 1729.22  5007.1 1729.22  5014.7 1730.87  5093.3 1733.24  5098.4 1732.49
  5116.1 1732.91  5159.2 1734.61  5207.4 1737.34    5215 1738.15    5220 1737.71
  5268.2 1741.18  5275.8 1742.49  5280.9 1742.25  5298.6 1745.05  5308.7 1745.85
#Mann= 4 ,-1 , 0
  4580.3    .063       0  4845.4    .035       0  4974.3    .035       0
  4978.3    .035       0
Bank Sta=4974.3,4978.3
XS Rating Curve= 0 ,0
Exp/Cntr=0.3,0.1

Type RM Length L Ch R = 1 ,1832    ,390,390,390
BEGIN DESCRIPTION:
Stream QC-1 4.0
END DESCRIPTION:
XS GIS Cut Line= 3
        1930375.     13935375.01        1930125.       13935075.
      1929924.98     13935125.01
#Sta/Elev= 30
  4603.6 1737.91  4610.8 1737.43  4617.3 1737.71  4645.9 1734.35  4703.2 1730.54
  4738.3 1729.28  4787.8 1726.51  4816.4 1725.72  4873.7  1722.5  4966.1 1718.98
  4980.5 1718.88  4990.9 1716.45  4996.7 1716.45  5002.4 1715.49  5002.7 1714.99
  5006.2 1714.99  5006.4 1715.49    5020 1716.16    5025 1716.97  5035.4 1719.92
  5053.4 1722.73  5066.3 1723.44  5128.1 1724.18    5159 1725.16  5169.4  1726.1
  5177.1 1731.61  5182.2 1729.33    5190 1731.03  5197.7 1727.22  5200.3 1727.22
#Mann= 4 ,-1 , 0
  4603.6    .035       0  5002.4    .035       0  5006.4    .035       0
    5020    .063       0
Bank Sta=5002.4,5006.4
XS Rating Curve= 0 ,0
Exp/Cntr=0.3,0.1

Type RM Length L Ch R = 1 ,1442    ,171,171,171
BEGIN DESCRIPTION:
Stream QC-1 3.0
END DESCRIPTION:
XS GIS Cut Line= 4
      1930424.99     13934924.99      1930347.33     13934769.66
      1930269.31     13934731.96        1929925.       13934775.
#Sta/Elev= 30
  4776.1 1721.19    4814 1720.73  4829.2 1718.91  4851.6 1719.07  4857.1 1716.96
  4873.9    1717  4879.5 1716.27  4887.9 1716.55  4924.2 1715.32    4941 1713.94
  4970.5 1713.97    4976 1711.81  4985.7 1712.19  4994.4 1711.72  5007.9 1710.11
  5019.2 1709.84  5019.5 1709.34    5023 1709.34  5023.2 1709.84    5036 1712.55
  5041.1 1712.55  5081.1 1715.86  5097.3 1716.44  5141.5 1718.02  5179.3  1718.6
  5242.3 1718.65  5292.7 1717.72  5337.7 1720.09  5355.1 1720.91  5383.4 1721.08
#Mann= 8 ,-1 , 0
  4776.1    .094       0    4814    .035       0  4994.4    .063       0
  5019.2     .05       0  5023.2    .063       0  5097.3     .12       0
  5337.7    .094       0  5355.1     .12       0
#XS Ineff= 2 , 0
         4985.65 1716.47 5035.87         1716.55
Permanent Ineff=
       F       F
Bank Sta=5019.2,5023.2
XS Rating Curve= 0 ,0
Exp/Cntr=0.3,0.1

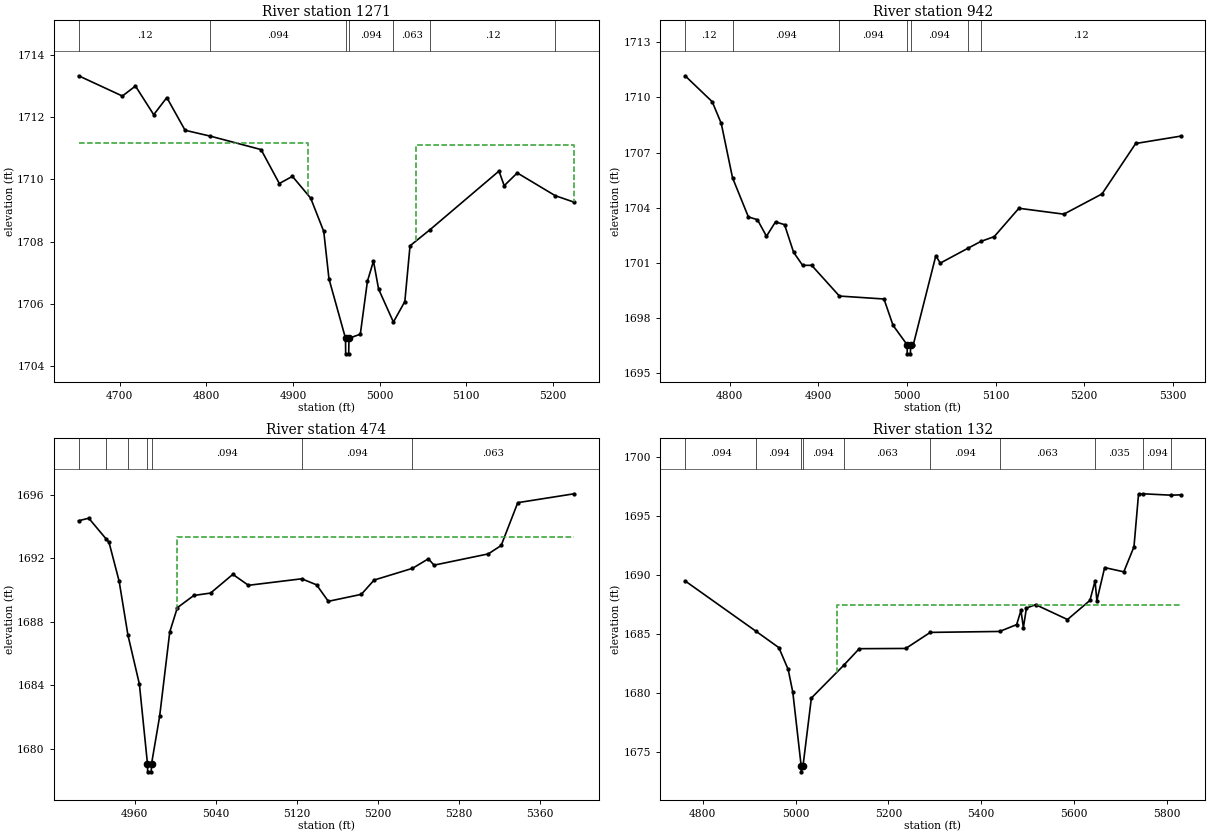
Type RM Length L Ch R = 1 ,1271    ,329,329,329
BEGIN DESCRIPTION:
Mapping XS bb5ac5ae
END DESCRIPTION:
XS GIS Cut Line= 2
      1930714.56     13934816.05      1930234.92     13934504.21
#Sta/Elev= 30
  4652.6 1713.33  4703.1 1712.68  4718.2    1713  4739.3 1712.08  4754.4 1712.63
  4775.5 1711.58  4804.8 1711.39  4863.2 1710.96  4884.3 1709.87  4899.4  1710.1
  4920.5  1709.4  4935.6 1708.33  4941.6 1706.81  4960.7  1704.9  4960.9  1704.4
  4964.4  1704.4  4964.7  1704.9  4977.8 1705.03    4986 1706.73    4993 1707.38
  4998.9 1706.48    5016 1705.42  5029.2 1706.08  5035.2 1707.87  5058.4 1708.39
  5137.9 1710.27  5143.9  1709.8    5159 1710.21  5202.8 1709.48  5224.7 1709.27
#Mann= 7 ,-1 , 0
  4652.6     .12       0  4804.8    .094       0  4960.7     .05       0
  4964.7    .094       0    5016    .063       0  5058.4     .12       0
  5202.8    .094       0
#XS Ineff= 2 , 0
         4917.83 1711.16  5042.6         1711.11
Permanent Ineff=
       F       F
Bank Sta=4960.7,4964.7
XS Rating Curve= 0 ,0
Exp/Cntr=0.3,0.1

Type RM Length L Ch R = 1 ,942     ,468,468,468
BEGIN DESCRIPTION:
Stream QC-1 2.0
END DESCRIPTION:
XS GIS Cut Line= 3
      1930725.01     13934675.03        1930675.       13934425.
      1930375.02       13934375.
#Sta/Elev= 30
  4749.7 1711.17  4780.3 1709.76  4790.5 1708.58  4803.2 1705.63  4821.1  1703.5
  4831.3 1703.35  4841.5 1702.45  4851.7 1703.23  4861.9 1703.08  4872.1 1701.58
  4882.3 1700.87  4892.5 1700.87  4923.8  1699.2  4974.1 1699.04  4984.3 1697.61
  5000.1 1696.56  5000.4 1696.06  5003.9 1696.06  5004.1 1696.56  5007.2 1696.56
  5032.6 1701.39  5037.6 1700.99  5069.3 1701.81  5083.5 1702.17  5098.5 1702.43
  5126.3 1703.97    5177 1703.65  5220.1 1704.75  5258.1 1707.49  5308.8 1707.89
#Mann= 7 ,-1 , 0
  4749.7     .12       0  4803.2    .094       0  4923.8    .094       0
  5000.1     .05       0  5004.1    .094       0  5069.3    .094       0
  5083.5     .12       0
Bank Sta=5000.1,5004.1
XS Rating Curve= 0 ,0
Exp/Cntr=0.3,0.1

Type RM Length L Ch R = 1 ,474     ,342,342,342
BEGIN DESCRIPTION:
Stream QC-1 1.0
END DESCRIPTION:
XS GIS Cut Line= 3
        1931025.     13934224.96        1931025.       13934125.
      1930679.86     13933944.62
#Sta/Elev= 30
  4904.8 1694.37  4914.8 1694.53  4931.6 1693.25  4934.8 1693.01  4944.8 1690.56
  4953.5 1687.16  4964.8 1684.07  4972.8 1679.04    4973 1678.54  4976.5 1678.54
  4976.8 1679.04  4984.8 1682.04  4994.8 1687.36  5002.3 1688.89  5018.6 1689.66
  5035.1 1689.81  5057.1 1690.99  5072.5  1690.3  5125.1 1690.71  5139.8 1690.33
  5151.4 1689.29    5184 1689.73  5196.6 1690.63  5234.5 1691.37  5250.2 1691.97
  5255.8 1691.57  5309.4 1692.28  5322.1 1692.81  5338.5 1695.51  5394.2 1696.07
#Mann= 7 ,-1 , 0
  4904.8    .063       0  4931.6    .035       0  4953.5    .094       0
  4972.8     .05       0  4976.8    .094       0  5125.1    .094       0
  5234.5    .063       0
#XS Ineff= 2 , 0
                         5001.46         1693.36
Permanent Ineff=
       F       F
Bank Sta=4972.8,4976.8
XS Rating Curve= 0 ,0
Exp/Cntr=0.3,0.1

Type RM Length L Ch R = 1 ,132     ,0,0,0
BEGIN DESCRIPTION:
Stream QC-1 0.0
END DESCRIPTION:
XS GIS Cut Line= 3
      1931310.63     13934186.98      1931299.03     13933898.19
      1930559.49     13933652.87
#Sta/Elev= 30
  4761.7 1689.53  4914.4 1685.27  4963.8 1683.88  4983.9 1682.03  4993.9  1680.1
  5011.9 1673.86  5012.1 1673.36  5015.9 1673.86  5033.9 1679.61    5104  1682.4
  5137.1 1683.79  5237.4 1683.81  5290.2 1685.17  5439.8 1685.25  5476.4 1685.83
  5485.7 1687.03  5490.9 1685.58  5497.5 1687.23  5517.3 1687.52    5586 1686.26
  5634.4 1687.88  5645.4 1689.53  5649.3 1687.86  5666.1 1690.66  5707.4  1690.3
  5729.3 1692.42  5739.1 1696.86  5748.2 1696.91  5809.8 1696.79  5829.9 1696.82
#Mann= 10 ,-1 , 0
  4761.7    .094       0  4914.4    .094       0  5011.9     .05       0
  5015.9    .094       0    5104    .063       0  5290.2    .094       0
  5439.8    .063       0  5645.4    .035       0  5748.2    .094       0
  5809.8     .12       0
#XS Ineff= 2 , 0
                         5088.12         1687.53
Permanent Ineff=
       F       F
Bank Sta=5011.9,5015.9
XS Rating Curve= 0 ,0
Exp/Cntr=0.3,0.1

Chan Stop Cuts=-1
Use User Specified Reach Order=0
Composite Channel Slope=5