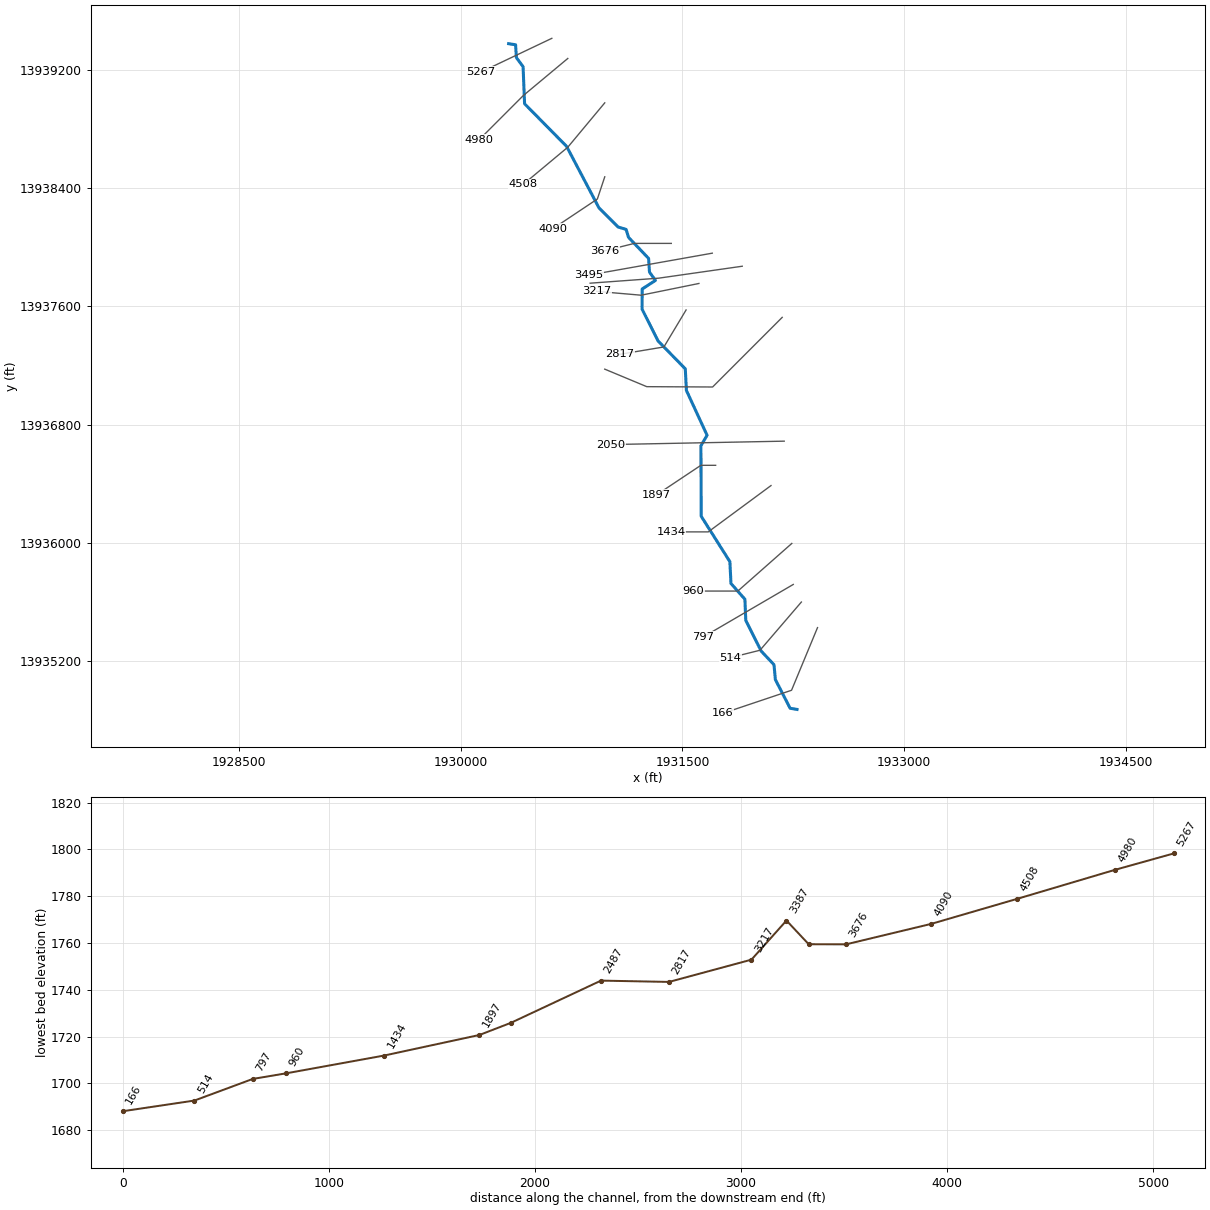
--- Stream QC-2.prj (project) ---

Proj Title=Stream QC-2 Base Level Engineering
Current Plan=p01
Default Exp/Contr=0.3,0.1
English Units
Geom File=g01
Flow File=f01
Plan File=p01
Y Axis Title=Elevation
X Axis Title(PF)=Main Channel Distance
X Axis Title(XS)=Station
BEGIN DESCRIPTION:
Stream QC-2
END DESCRIPTION:
DSS Export Rating Curves= 0
DSS Export Rating Curve Sorted= 0
DSS Export Volume Flow Curves= 0
DXF OffsetX= 0
DXF OffsetY= 0
DXF ScaleX= 1
DXF ScaleY= 10

--- Stream QC-2.p01 (plan) ---

Plan Title=Multiple Run
Short Identifier=Multiple
Geom File=g01
Flow File=f01
Subcritical Flow
K Sum by GR= 0
Std Step Tol= 0.01
Critical Tol= 0.01
Num of Std Step Trials= 20
Max Error Tol= 0.3
Flow Tol Ratio= 0.001
Split Flow NTrial= 30
Split Flow Tol= 0.02
Split Flow Ratio= 0.02
Log Output Level= 0
Friction Slope Method= 1
Unsteady Friction Slope Method= 2
Unsteady Bridges Friction Slope Method= 1
Parabolic Critical Depth
Global Vel Dist=  1 , 1 , 1
Global Log Level= 0
CheckData=True
Encroach Param= -1, 0, 0, 0
BEGIN DESCRIPTION:
Multiple Run
END DESCRIPTION:

--- Stream QC-2.f01 (steady flow) ---

Flow Title=Multiple
Program Version=4.10
Number of Profiles= 7
Profile Names=10-year,25-year,50-year,1pct_min,100-year,1pct_plu,500-year
River Rch & RM=Stream QC-2,Reach-1         ,5267
     991    1685    2345    1581    3154    6293    5627
River Rch & RM=Stream QC-2,Reach-1         ,2050
    1066    1819    2538    1714    3420    6823    6125
Boundary for River Rch & Prof#=Stream QC-2,Reach-1         , 1
Up Type= 0
Dn Type= 3
Dn Slope=0.01
Boundary for River Rch & Prof#=Stream QC-2,Reach-1         , 2
Up Type= 0
Dn Type= 3
Dn Slope=0.01
Boundary for River Rch & Prof#=Stream QC-2,Reach-1         , 3
Up Type= 0
Dn Type= 3
Dn Slope=0.01
Boundary for River Rch & Prof#=Stream QC-2,Reach-1         , 4
Up Type= 0
Dn Type= 3
Dn Slope=0.01
Boundary for River Rch & Prof#=Stream QC-2,Reach-1         , 5
Up Type= 0
Dn Type= 3
Dn Slope=0.01
Boundary for River Rch & Prof#=Stream QC-2,Reach-1         , 6
Up Type= 0
Dn Type= 3
Dn Slope=0.01
Boundary for River Rch & Prof#=Stream QC-2,Reach-1         , 7
Up Type= 0
Dn Type= 3
Dn Slope=0.01
DSS Import GetInterval= 0
DSS Import GetPeak= 0
DSS Import FillOption= 0

--- Stream QC-2.g01 (geometry) ---

Geom Title=Existing Conditions
Program Version=4.10

River Reach=Stream QC-2     ,Reach-1
Reach XY= 30
        1930325.       13939375.      1930372.02     13939367.55
      1930377.31     13939281.01      1930422.74     13939219.07
      1930432.81     13938968.81      1930716.86     13938681.06
      1930935.78     13938265.32      1931065.58     13938135.89
      1931119.38     13938119.38      1931135.89     13938065.58
      1931271.39      13937923.5      1931277.57     13937830.88
      1931317.74      13937774.7      1931228.11     13937716.69
      1931227.34     13937580.53      1931335.76     13937365.32
      1931519.53     13937177.45      1931527.27     13937030.94
      1931666.96     13936728.32      1931625.33     13936656.78
      1931627.35     13936180.52      1931821.24     13935873.44
      1931828.56     13935726.47      1931922.81     13935619.55
      1931928.76     13935476.56      1932033.16     13935268.95
      1932119.46     13935177.42      1932128.83     13935076.59
      1932228.41     13934882.99        1932275.       13934875.

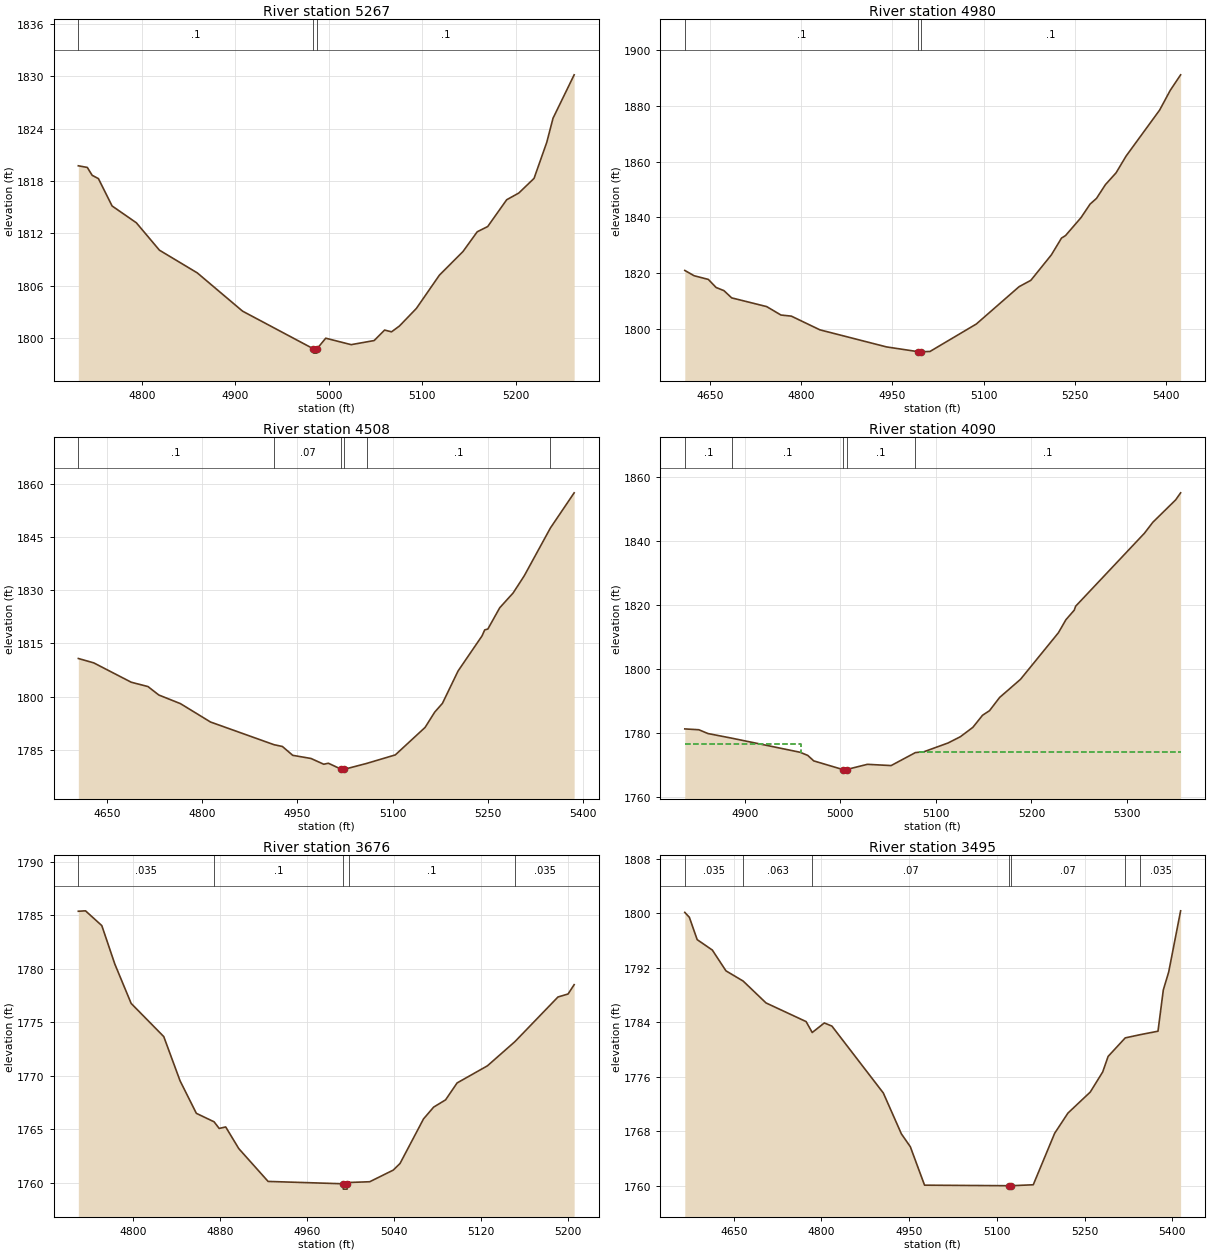
Type RM Length L Ch R = 1 ,5267    ,287,287,287
BEGIN DESCRIPTION:
Stream QC-2 12.0
END DESCRIPTION:
XS GIS Cut Line= 2
      1930617.09     13939411.06      1930137.95     13939183.34
#Sta/Elev= 30
  4732.1 1819.74  4741.7 1819.55  4746.9 1818.65  4753.6 1818.27  4768.2 1815.14
  4794.2 1813.21  4818.9 1810.07  4859.4 1807.47  4907.8 1803.09  4983.5 1798.78
  4983.8 1798.28  4987.3 1798.28  4987.5 1798.78  4996.8 1799.99    5024 1799.25
  5048.6 1799.72  5059.8 1800.92  5067.2 1800.72  5075.6 1801.38  5093.8  1803.4
  5118.4 1807.21  5143.6 1809.91  5158.9 1812.18  5170.1 1812.78  5190.4 1815.85
  5203.4 1816.62  5219.7  1818.3  5233.3 1822.43    5240 1825.19  5262.6 1830.16
#Mann= 3 ,-1 , 0
  4732.1      .1       0  4983.5     .05       0  4987.5      .1       0
Bank Sta=4983.5,4987.5
XS Rating Curve= 0 ,0
Exp/Cntr=0.3,0.1

Type RM Length L Ch R = 1 ,4980    ,472,472,472
BEGIN DESCRIPTION:
Stream QC-2 11.0
END DESCRIPTION:
XS GIS Cut Line= 3
      1930724.99     13939274.99        1930425.       13939025.
      1930125.04     13938725.04
#Sta/Elev= 30
  4608.9 1820.92  4624.2 1819.02  4647.6 1817.69  4660.4 1814.79  4673.2 1813.67
  4685.9 1811.07  4743.5 1807.93  4766.9 1804.91    4784 1804.51  4830.9 1799.59
  4940.2 1793.47  4992.7 1791.73  4992.9 1791.23  4996.7 1791.73  5011.8 1791.83
  5087.9 1801.68  5158.2 1815.09  5177.5 1817.37  5211.2  1826.5  5227.9 1832.54
  5234.5 1833.44    5260  1839.9  5274.8 1844.73  5285.4 1846.79    5300 1851.71
  5317.6 1855.98  5333.9 1861.95  5389.1 1878.49  5406.6 1885.59  5423.6 1891.15
#Mann= 3 ,-1 , 0
  4608.9      .1       0  4992.7     .05       0  4996.7      .1       0
Bank Sta=4992.7,4996.7
XS Rating Curve= 0 ,0
Exp/Cntr=0.3,0.1

Type RM Length L Ch R = 1 ,4508    ,418,418,418
BEGIN DESCRIPTION:
Stream QC-2 10.0
END DESCRIPTION:
XS GIS Cut Line= 3
      1930975.01     13938975.01        1930725.       13938675.
      1930425.03     13938425.03
#Sta/Elev= 30
  4604.9 1810.75  4629.2 1809.51  4688.2 1804.04  4714.6 1802.81  4731.7 1800.42
  4765.8 1797.98  4813.1 1792.79    4913 1786.38  4926.4 1785.86  4942.6 1783.37
  4971.3 1782.48  4991.5 1780.85  4998.8 1781.13  5019.4  1779.4  5019.6  1778.9
  5023.4  1779.4  5059.1 1781.08  5104.2 1783.49  5151.1 1791.26  5166.2 1795.57
  5178.4 1798.06  5203.1 1807.23  5240.8 1817.14    5245 1818.83    5250 1819.09
  5268.7  1825.1  5289.8 1829.28  5307.3 1834.13  5348.5 1847.65  5385.9 1857.59
#Mann= 6 ,-1 , 0
  4604.9      .1       0    4913     .07       0  5019.4     .05       0
  5023.4     .07       0  5059.1      .1       0  5348.5     .07       0
Bank Sta=5019.4,5023.4
XS Rating Curve= 0 ,0
Exp/Cntr=0.3,0.1

Type RM Length L Ch R = 1 ,4090    ,414,414,414
BEGIN DESCRIPTION:
Stream QC-2 9.0
END DESCRIPTION:
XS GIS Cut Line= 3
      1930975.01     13938475.02        1930925.       13938325.
      1930625.07     13938125.05
#Sta/Elev= 30
  4837.4 1781.34  4852.1 1781.08  4861.6  1779.9  4887.1 1778.42    4958 1774.06
    4966 1773.08  4972.3 1771.37  5002.6 1768.68  5002.9 1768.18  5006.4 1768.18
  5006.6 1768.68  5028.4  1770.3  5053.2 1769.91  5078.6 1773.96  5087.5 1774.22
  5112.8 1776.96  5125.7 1778.92  5138.7 1781.83  5148.8 1785.59  5156.1 1787.02
  5166.7 1791.15  5188.5 1796.79  5228.2 1811.33    5236 1815.37  5244.7 1818.35
  5246.2 1819.59  5318.2 1842.36  5326.9 1845.75  5350.8 1852.74    5356 1854.94
#Mann= 5 ,-1 , 0
  4837.4      .1       0  4887.1      .1       0  5002.6     .05       0
  5006.6      .1       0  5078.6      .1       0
#XS Ineff= 2 , 0
         4959.44 1776.77 5082.26         1774.14
Permanent Ineff=
       F       F
Bank Sta=5002.6,5006.6
XS Rating Curve= 0 ,0
Exp/Cntr=0.3,0.1

Type RM Length L Ch R = 1 ,3676    ,181,181,181
BEGIN DESCRIPTION:
Stream QC-2 8.0
END DESCRIPTION:
XS GIS Cut Line= 3
      1931425.02       13938025.        1931175.       13938025.
      1930974.98       13937975.
#Sta/Elev= 30
  4749.8 1785.38  4756.4 1785.42  4771.4 1784.04  4783.4 1780.44  4798.4 1776.77
  4828.4 1773.67  4843.4 1769.54  4858.4  1766.5  4874.7 1765.71  4879.4 1765.09
  4885.4 1765.23  4897.4 1763.21  4924.4 1760.14  4993.4 1759.92  4993.6 1759.42
  4997.1 1759.42  4997.4 1759.92  4998.4 1760.04  5017.9 1760.11  5039.6  1761.2
  5045.8 1761.82  5067.4 1765.98  5076.7 1767.08  5087.7 1767.76  5098.3 1769.34
  5126.2 1770.94  5151.6 1773.21  5191.1 1777.37  5200.4 1777.65    5206 1778.52
#Mann= 5 ,-1 , 0
  4749.8    .035       0  4874.7      .1       0  4993.6     .05       0
  4998.4      .1       0  5151.6    .035       0
Bank Sta=4993.4,4997.4
XS Rating Curve= 0 ,0
Exp/Cntr=0.3,0.1

Type RM Length L Ch R = 1 ,3495    ,108,108,108
BEGIN DESCRIPTION:
Stream QC-2 7.1
END DESCRIPTION:
XS GIS Cut Line= 2
      1931702.16      13937958.9      1930867.31      13937810.7
#Sta/Elev= 30
  4566.3 1800.09  4574.1 1799.37  4587.5 1796.09  4613.4 1794.56  4636.7 1791.51
  4666.1 1790.01  4705.2  1786.8  4773.8 1784.06  4784.2 1782.46  4804.9 1783.86
  4817.9  1783.4  4905.8 1773.58  4936.7 1767.58    4952 1765.69  4976.3 1760.05
  5120.6 1759.97  5120.8 1759.47  5124.6 1759.97  5162.2 1760.11  5198.8 1767.67
  5221.5 1770.63  5259.7 1773.72    5281 1776.68  5290.2 1778.95  5319.5 1781.67
  5345.5 1782.15  5375.5 1782.65  5384.6 1788.71  5393.8 1791.34  5414.2 1800.32
#Mann= 7 ,-1 , 0
  4566.3    .035       0  4666.1    .063       0  4784.2     .07       0
  5120.8     .05       0  5124.6     .07       0  5319.5    .063       0
  5345.5    .035       0
Bank Sta=5120.6,5124.6
XS Rating Curve= 0 ,0
Exp/Cntr=0.3,0.1

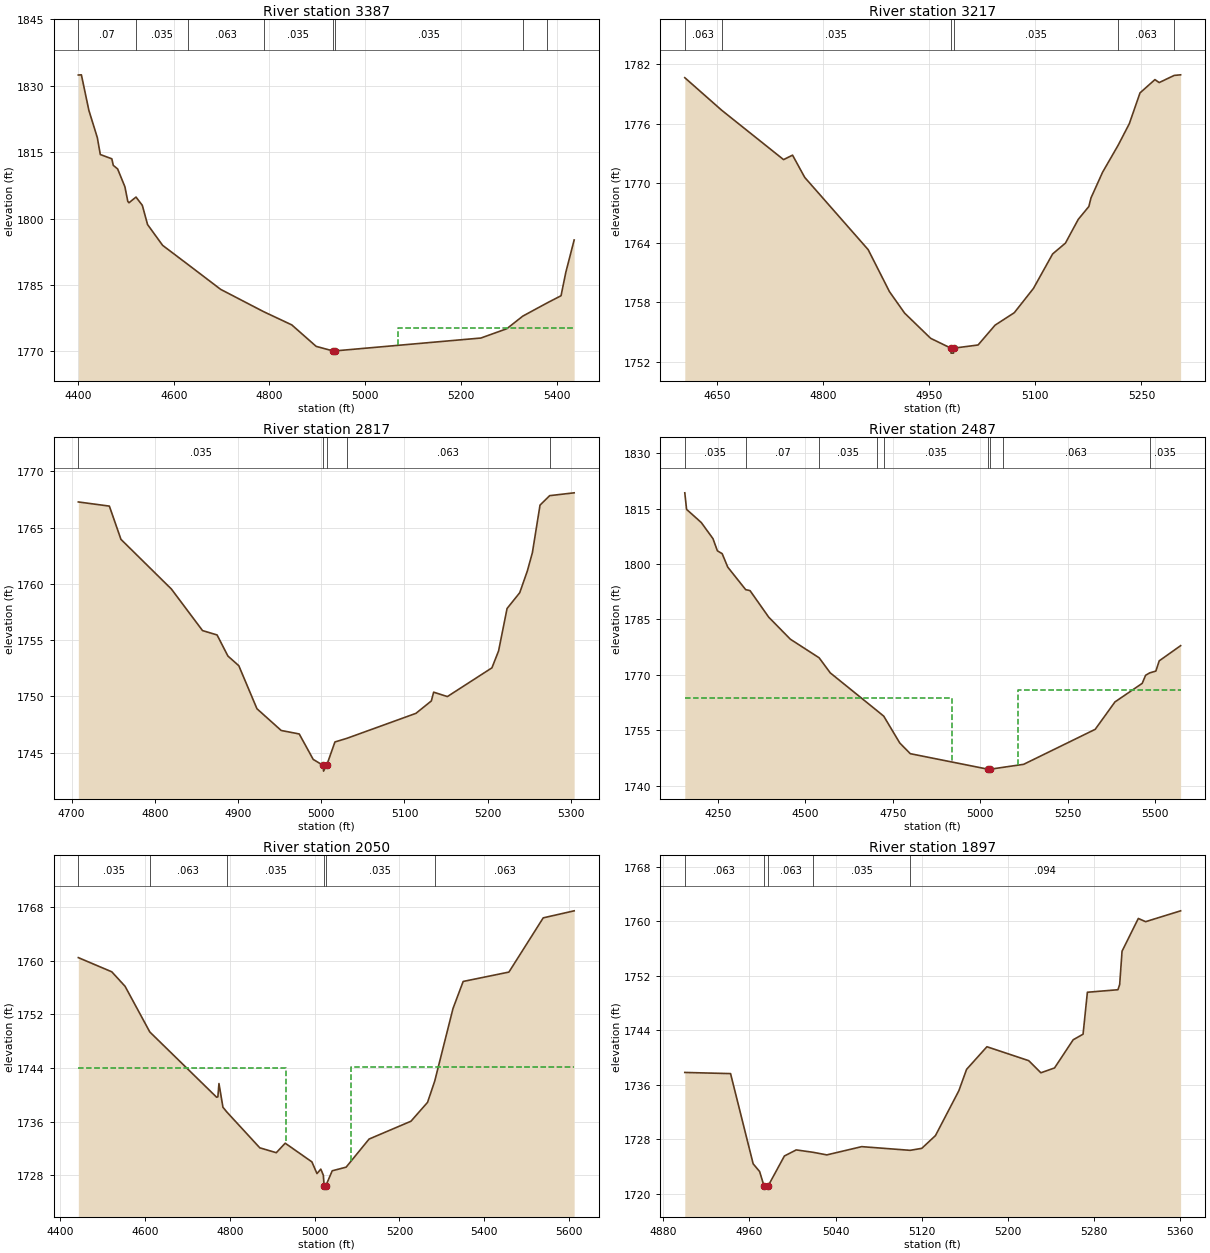
Type RM Length L Ch R = 1 ,3387    ,170,170,170
BEGIN DESCRIPTION:
Stream QC-2 7.2
END DESCRIPTION:
XS GIS Cut Line= 3
      1931904.75     13937870.65      1931339.62     13937789.92
      1930876.12     13937756.07
#Sta/Elev= 30
  4400.8 1832.42  4407.2 1832.46  4422.8 1824.45  4440.5 1818.26  4446.7 1814.46
  4470.8 1813.49  4473.8 1812.01  4482.9  1811.2  4498.1 1807.17  4504.1 1803.89
  4506.5 1803.56  4521.3 1804.85  4534.5 1802.97  4545.4 1798.64  4576.9 1793.94
  4630.4 1789.57  4698.1    1784  4787.9 1778.96  4846.6 1775.98  4897.5 1771.13
  4932.5  1770.1  4932.7  1769.6  4936.5  1770.1  5241.6 1773.01  5295.7 1775.11
  5329.1 1777.96  5380.3 1780.96    5409 1782.56    5419 1787.86  5436.4 1795.16
#Mann= 8 ,-1 , 0
  4400.8     .07       0  4521.3    .035       0  4630.4    .063       0
  4787.9    .035       0  4932.5    .035       0  4936.5    .035       0
  5329.1    .063       0  5380.3    .035       0
#XS Ineff= 2 , 0
                         5068.93         1775.33
Permanent Ineff=
       F       F
Bank Sta=4932.5,4936.5
XS Rating Curve= 0 ,0
Exp/Cntr=0.3,0.1

Type RM Length L Ch R = 1 ,3217    ,400,400,400
BEGIN DESCRIPTION:
Stream QC-2 7.0
END DESCRIPTION:
XS GIS Cut Line= 3
      1931611.95     13937754.14      1931221.27     13937674.79
      1930920.24     13937700.78
#Sta/Elev= 30
  4604.5 1780.62  4656.7 1777.34  4744.1 1772.37  4756.8 1772.82    4774 1770.58
  4863.7  1763.3  4893.8 1759.07  4915.2 1756.91    4952 1754.37  4980.6 1753.38
  4980.8 1752.88  4984.3 1752.88  4984.6 1753.38    5019  1753.7  5043.1  1755.7
  5070.2 1756.95  5097.3  1759.4  5124.4 1762.87  5142.5 1763.96  5160.6 1766.35
  5175.6 1767.65  5178.6 1768.51    5195  1771.1    5217 1773.82  5232.8 1775.99
  5247.9 1779.09    5269 1780.43    5275 1780.13  5296.2 1780.85  5305.3 1780.91
#Mann= 6 ,-1 , 0
  4604.5    .063       0  4656.7    .035       0  4980.6    .035       0
  4984.6    .035       0    5217    .063       0  5296.2    .035       0
Bank Sta=4980.6,4984.6
XS Rating Curve= 0 ,0
Exp/Cntr=0.3,0.1

Type RM Length L Ch R = 1 ,2817    ,330,330,330
BEGIN DESCRIPTION:
Stream QC-2 6.0
END DESCRIPTION:
XS GIS Cut Line= 3
      1931524.98     13937574.97        1931375.       13937325.
      1931074.95     13937274.99
#Sta/Elev= 30
  4708.2 1767.27  4745.5  1766.9  4759.4 1763.95  4820.1 1759.53  4857.4 1755.85
  4874.9 1755.46  4887.9 1753.59    4901 1752.73  4922.8 1748.91  4951.9 1746.98
  4973.6 1746.67  4990.4 1744.41  5002.5 1743.87  5002.8 1743.37  5006.5 1743.87
  5016.5 1745.96  5030.8 1746.28  5113.8  1748.5  5132.3  1749.6  5135.1 1750.38
  5151.6 1749.99  5205.1 1752.54  5213.1 1754.04  5223.3 1757.81  5238.5 1759.21
  5247.6 1761.13  5253.7 1762.76  5262.9 1766.99  5274.5 1767.83  5303.9 1768.08
#Mann= 5 ,-1 , 0
  4708.2    .035       0  5002.5    .035       0  5006.5    .035       0
  5030.8    .063       0  5274.5    .035       0
Bank Sta=5002.5,5006.5
XS Rating Curve= 0 ,0
Exp/Cntr=0.3,0.1

Type RM Length L Ch R = 1 ,2487    ,437,437,437
BEGIN DESCRIPTION:
Stream QC-2 5.0
END DESCRIPTION:
XS GIS Cut Line= 4
      1932175.02     13937525.02      1931704.35     13937054.35
      1931259.13     13937056.61      1930974.96     13937175.02
#Sta/Elev= 30
  4154.7  1819.3  4159.8 1814.82  4201.8 1811.26  4235.3 1806.89    4248 1803.59
  4261.6 1802.83  4277.7 1799.17  4328.8 1793.09  4341.4 1792.81  4394.8 1785.63
  4456.7 1779.66  4539.1 1774.62  4570.9 1770.54  4705.8 1760.22  4723.9 1758.82
  4769.9 1751.54    4800 1748.65  5023.2 1744.43  5023.5 1743.93  5027.2 1744.43
  5063.8 1744.94  5124.2 1745.77    5329 1755.25  5385.5 1762.67  5463.5  1767.7
  5473.2 1769.89  5485.1 1770.54  5502.5 1771.02  5512.2  1773.8  5573.4 1777.91
#Mann= 9 ,-1 , 0
  4154.7    .035       0  4328.8     .07       0  4539.1    .035       0
  4705.8    .063       0  4723.9    .035       0  5023.2    .035       0
  5027.2    .035       0  5063.8    .063       0  5485.1    .035       0
#XS Ineff= 2 , 0
         4919.08 1763.79 5109.29         1765.87
Permanent Ineff=
       F       F
Bank Sta=5023.2,5027.2
XS Rating Curve= 0 ,0
Exp/Cntr=0.3,0.1

Type RM Length L Ch R = 1 ,2050    ,153,153,153
BEGIN DESCRIPTION:
Mapping XS 31a5cd8a
END DESCRIPTION:
XS GIS Cut Line= 2
      1932188.73     13936688.26      1931018.45     13936665.22
#Sta/Elev= 30
  4442.1 1760.48  4521.1 1758.36  4552.4  1756.2  4610.9 1749.37  4768.5 1739.63
  4771.5 1739.68  4774.1 1741.67  4783.5 1738.13    4793  1737.4  4870.5 1732.07
  4909.4 1731.34  4930.5 1732.76  4993.5 1729.97  5005.5 1728.22  5014.5 1728.89
  5020.5 1727.98  5022.3  1726.4  5022.5  1725.9  5026.3  1726.4  5041.5 1728.64
  5074.3 1729.18  5128.5 1733.38  5227.3 1736.04  5266.5 1738.86  5283.5 1742.05
  5326.6 1752.88  5350.6 1756.92  5458.6 1758.32  5539.6 1766.42  5612.6 1767.47
#Mann= 6 ,-1 , 0
  4442.1    .035       0  4610.9    .063       0    4793    .035       0
  5022.3    .035       0  5026.3    .035       0  5283.5    .063       0
#XS Ineff= 2 , 0
         4931.47 1743.95 5085.31         1744.15
Permanent Ineff=
       F       F
Bank Sta=5022.3,5026.3
XS Rating Curve= 0 ,0
Exp/Cntr=0.3,0.1

Type RM Length L Ch R = 1 ,1897    ,463,463,463
BEGIN DESCRIPTION:
Stream QC-2 4.0
END DESCRIPTION:
XS GIS Cut Line= 3
      1931724.97       13936525.        1931625.       13936525.
      1931325.02     13936325.01
#Sta/Elev= 30
    4900 1737.81  4942.5 1737.64  4963.5 1724.41  4969.5 1723.28  4973.5  1721.2
  4973.8  1720.7  4977.5  1721.2  4992.5 1725.56  5003.5 1726.45  5019.2  1726.1
  5031.9 1725.72  5064.3 1726.93  5109.3 1726.39  5120.1 1726.68  5132.8 1728.55
  5154.5 1735.12  5161.7 1738.26  5180.6 1741.58  5219.4 1739.54  5230.7 1737.76
  5243.4 1738.47  5260.7  1742.6  5269.9 1743.42  5273.9 1749.57  5302.3 1749.94
  5303.9 1750.71  5306.1 1755.59  5321.2 1760.39    5328 1759.92  5360.5 1761.51
#Mann= 5 ,-1 , 0
    4900    .063       0  4973.5     .05       0  4977.5    .063       0
  5019.2    .035       0  5109.3    .094       0
Bank Sta=4973.5,4977.5
XS Rating Curve= 0 ,0
Exp/Cntr=0.3,0.1

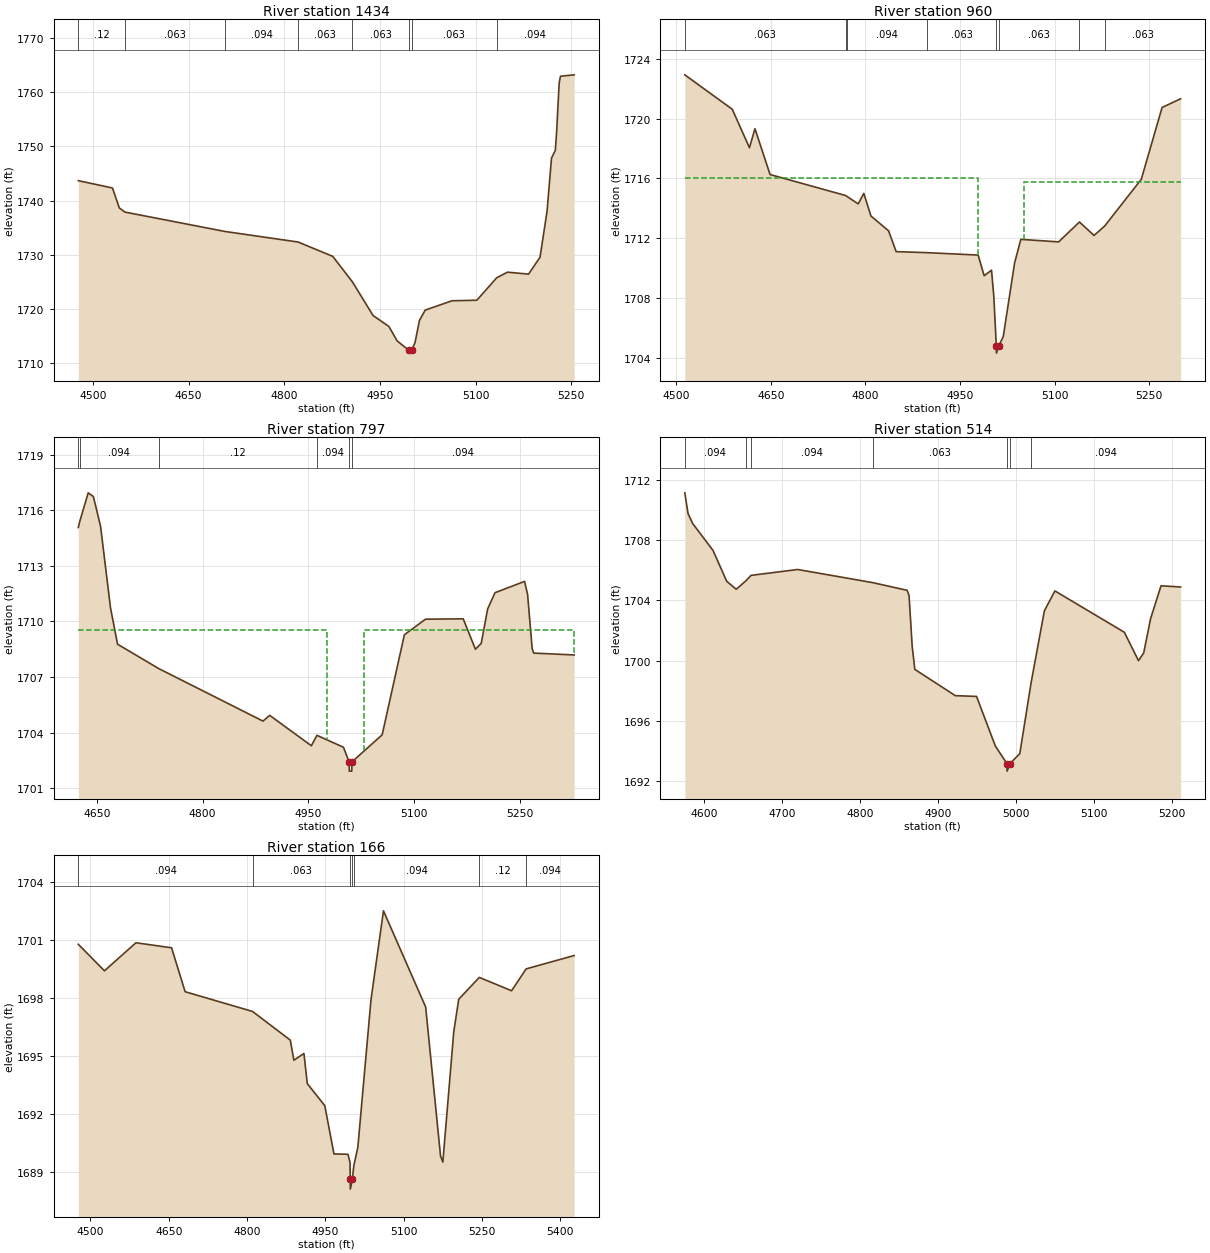
Type RM Length L Ch R = 1 ,1434    ,474,474,474
BEGIN DESCRIPTION:
Stream QC-2 3.0
END DESCRIPTION:
XS GIS Cut Line= 3
       1932099.3     13936388.05        1931675.       13936075.
      1931424.99       13936075.
#Sta/Elev= 30
  4477.2 1743.68  4530.7 1742.34  4541.5 1738.65  4550.4 1737.89  4707.2 1734.32
  4821.6 1732.38  4876.1 1729.73  4906.7 1725.06  4939.3 1718.83  4964.1 1716.81
    4977 1714.15  4995.7  1712.4  4995.9  1711.9  4999.7  1712.4    5005 1713.82
    5012 1717.93    5021 1719.83    5063 1721.55    5102 1721.65    5133 1725.78
    5150 1726.82    5183 1726.46    5201 1729.57    5212 1738.03    5219 1747.84
    5225 1749.28    5227 1752.62    5231 1761.63    5233 1762.93  5254.5 1763.19
#Mann= 8 ,-1 , 0
  4477.2     .12       0  4550.4    .063       0  4707.2    .094       0
  4821.6    .063       0  4906.7    .063       0  4995.7     .05       0
  4999.7    .063       0    5133    .094       0
Bank Sta=4995.7,4999.7
XS Rating Curve= 0 ,0
Exp/Cntr=0.3,0.1

Type RM Length L Ch R = 1 ,960     ,163,163,163
BEGIN DESCRIPTION:
Stream QC-2 2.0
END DESCRIPTION:
XS GIS Cut Line= 3
      1932239.93     13935996.87        1931875.       13935675.
      1931574.99       13935675.
#Sta/Elev= 30
  4513.4 1722.92  4588.7 1720.62    4616 1718.05  4624.7 1719.32  4648.7 1716.26
  4768.4 1714.86  4770.2 1714.81  4788.5  1714.3  4797.4    1715  4808.7 1713.49
  4836.7  1712.5  4848.7 1711.11  4898.1 1711.04  4978.8 1710.88  4988.3  1709.5
    5000 1709.87  5003.6 1708.14  5007.6 1704.83  5007.8 1704.33  5011.6 1704.83
  5018.6 1705.43  5036.6 1710.35  5046.5 1711.93  5106.5 1711.76  5139.5 1713.09
  5162.6 1712.19  5179.3 1712.81  5237.6 1715.94  5270.6 1720.74    5300 1721.32
#Mann= 8 ,-1 , 0
  4513.4    .063       0  4768.4     .12       0  4770.2    .094       0
  4898.1    .063       0  5007.6     .05       0  5011.6    .063       0
  5139.5    .094       0  5179.3    .063       0
#XS Ineff= 2 , 0
         4978.42 1716.02 5051.35         1715.77
Permanent Ineff=
       F       F
Bank Sta=5007.6,5011.6
XS Rating Curve= 0 ,0
Exp/Cntr=0.3,0.1

Type RM Length L Ch R = 1 ,797     ,283,283,283
BEGIN DESCRIPTION:
Stream QC-2 1.1
END DESCRIPTION:
XS GIS Cut Line= 2
      1932249.84     13935719.72      1931642.52     13935365.64
#Sta/Elev= 30
  4623.7 1715.07  4625.9 1715.42  4637.7 1716.94    4645 1716.74  4655.2 1715.14
  4669.3 1710.74  4679.3 1708.77  4737.9 1707.45  4885.5 1704.62    4895 1704.93
  4954.1 1703.29    4962 1703.85  4999.6 1703.21  5007.6 1702.42  5007.9 1701.92
  5011.4 1701.92  5011.6 1702.42  5054.5 1703.88    5086 1709.28  5115.9 1710.12
  5169.4 1710.14  5186.7  1708.5  5194.9 1708.81  5204.1 1710.68  5214.5 1711.55
  5256.4 1712.16  5260.7 1711.45  5267.2 1708.52  5269.4 1708.29  5326.7 1708.19
#Mann= 6 ,-1 , 0
  4623.7     .12       0  4625.9    .094       0  4737.9     .12       0
    4962    .094       0  5007.6     .05       0  5011.6    .094       0
#XS Ineff= 2 , 0
         4975.62 1709.52 5028.37         1709.52
Permanent Ineff=
       F       F
#Block Obstruct= 2 , 0
                         5149.85         1709.31
Bank Sta=5007.6,5011.6
XS Rating Curve= 0 ,0
Exp/Cntr=0.3,0.1

Type RM Length L Ch R = 1 ,514     ,348,348,348
BEGIN DESCRIPTION:
Stream QC-2 1.0
END DESCRIPTION:
XS GIS Cut Line= 3
      1932304.59     13935600.76        1932025.       13935275.
      1931825.04     13935225.01
#Sta/Elev= 30
  4575.7 1711.12  4579.9 1709.74  4585.9 1709.08  4611.8 1707.31  4629.4 1705.26
  4641.6 1704.73    4654 1705.29  4660.6 1705.65  4720.3 1706.04  4816.5 1705.17
  4860.7 1704.66  4863.1 1704.31  4867.1 1700.95  4870.5 1699.42  4922.4 1697.68
  4949.6 1697.63  4973.6 1694.35  4988.5 1693.18  4988.7 1692.68  4992.5 1693.18
    5005 1693.84  5019.6 1698.57  5036.5  1703.3    5050 1704.62    5139 1701.88
  5157.1    1700  5163.8 1700.51  5172.6 1702.78    5186 1704.96  5211.1 1704.88
#Mann= 7 ,-1 , 0
  4575.7    .094       0    4654    .063       0  4660.6    .094       0
  4816.5    .063       0  4988.5     .05       0  4992.5    .063       0
  5019.6    .094       0
#Block Obstruct= 2 , 0
                         5070.63         1702.03
Bank Sta=4988.5,4992.5
XS Rating Curve= 0 ,0
Exp/Cntr=0.3,0.1

Type RM Length L Ch R = 1 ,166     ,0,0,0
BEGIN DESCRIPTION:
Stream QC-2 0.0
END DESCRIPTION:
XS GIS Cut Line= 3
      1932413.84     13935427.95      1932238.16     13935004.42
      1931772.89     13934848.25
#Sta/Elev= 30
    4477 1700.77    4527  1699.4  4587.3 1700.85  4655.5 1700.59  4681.5 1698.32
  4810.6  1697.3  4882.8 1695.82  4889.7 1694.78  4908.9 1695.13  4915.4 1693.57
  4948.9 1692.43  4966.4 1689.94  4993.2 1689.92  4997.2  1689.5  4997.6 1688.62
  4997.8 1688.12  5001.6 1688.62  5004.4 1689.32  5012.2 1690.29  5037.3  1697.9
  5061.2  1702.5    5142 1697.53  5170.5 1689.83  5174.9 1689.52  5195.8 1696.25
  5205.3 1697.93  5244.7 1699.06  5306.5 1698.37  5334.4  1699.5  5426.3 1700.19
#Mann= 7 ,-1 , 0
    4477    .094       0  4810.6    .063       0  4997.6     .05       0
  5001.6    .063       0  5004.4    .094       0  5244.7     .12       0
  5334.4    .094       0
#Block Obstruct= 2 , 0
                         5077.32         1697.29
Bank Sta=4997.6,5001.6
XS Rating Curve= 0 ,0
Exp/Cntr=0.3,0.1

Chan Stop Cuts=-1
Use User Specified Reach Order=0
Composite Channel Slope=5