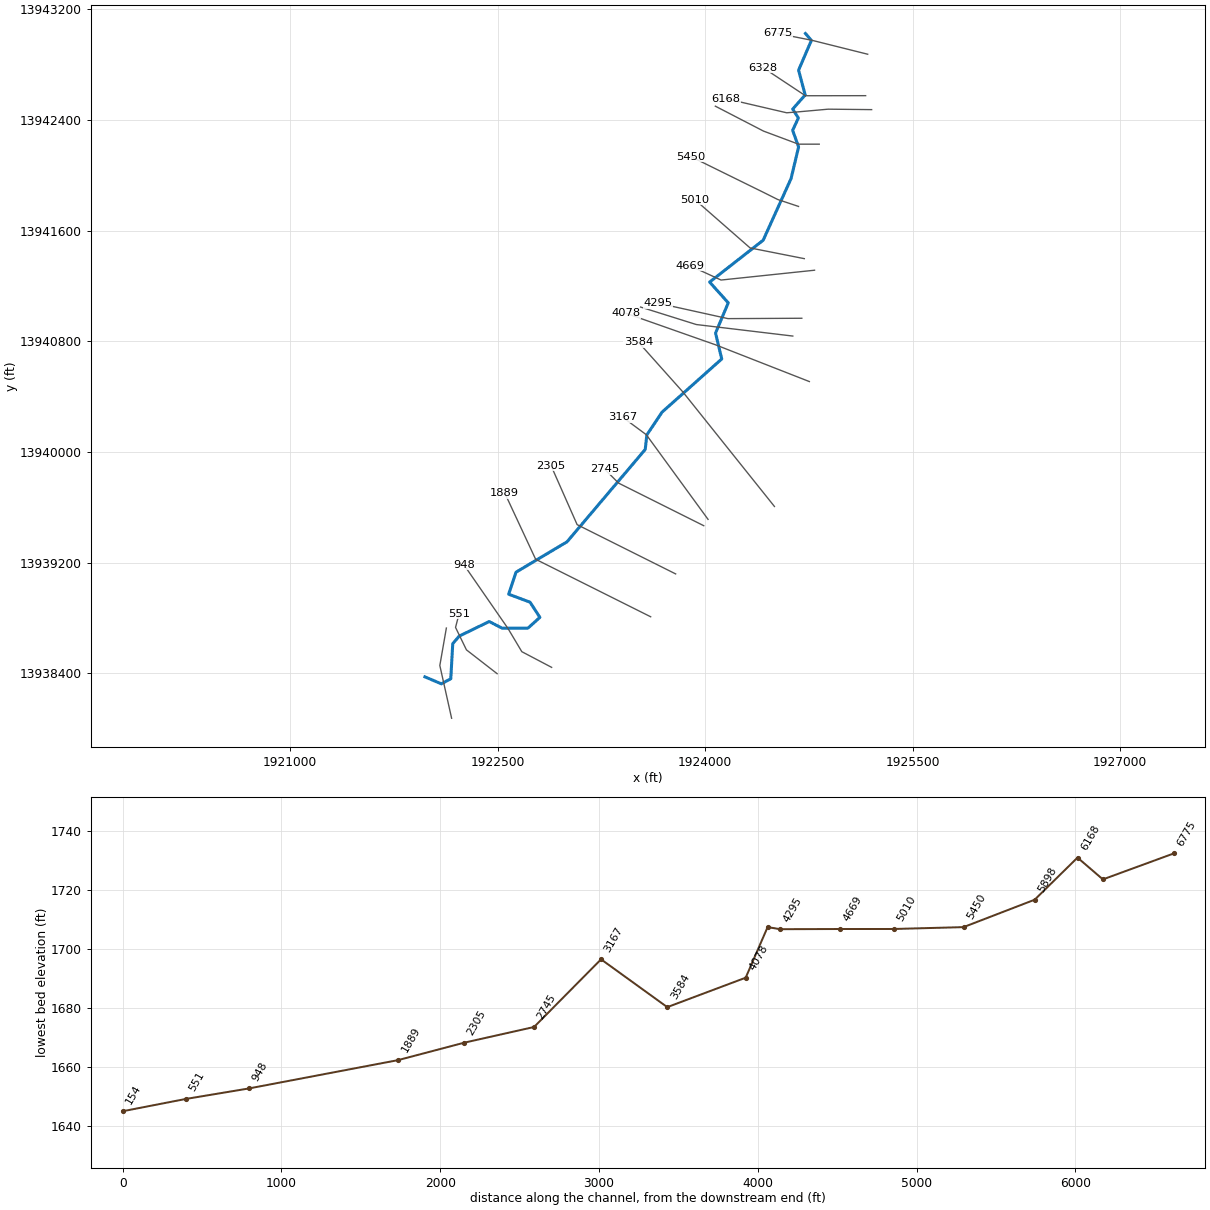
--- Stream TC-1.prj (project) ---

Proj Title=Stream TC-1 Base Level Engineering
Current Plan=p01
Default Exp/Contr=0.3,0.1
English Units
Geom File=g01
Flow File=f01
Plan File=p01
Y Axis Title=Elevation
X Axis Title(PF)=Main Channel Distance
X Axis Title(XS)=Station
BEGIN DESCRIPTION:
Stream TC-1
END DESCRIPTION:
DSS Export Rating Curves= 0
DSS Export Rating Curve Sorted= 0
DSS Export Volume Flow Curves= 0
DXF OffsetX= 0
DXF OffsetY= 0
DXF ScaleX= 1
DXF ScaleY= 10

--- Stream TC-1.p01 (plan) ---

Plan Title=Multiple Run
Short Identifier=Multiple
Geom File=g01
Flow File=f01
Subcritical Flow
K Sum by GR= 0
Std Step Tol= 0.01
Critical Tol= 0.01
Num of Std Step Trials= 20
Max Error Tol= 0.3
Flow Tol Ratio= 0.001
Split Flow NTrial= 30
Split Flow Tol= 0.02
Split Flow Ratio= 0.02
Log Output Level= 0
Friction Slope Method= 1
Unsteady Friction Slope Method= 2
Unsteady Bridges Friction Slope Method= 1
Parabolic Critical Depth
Global Vel Dist=  1 , 1 , 1
Global Log Level= 0
CheckData=True
Encroach Param= -1, 0, 0, 0
BEGIN DESCRIPTION:
Multiple Run
END DESCRIPTION:

--- Stream TC-1.f01 (steady flow) ---

Flow Title=Multiple
Program Version=4.10
Number of Profiles= 7
Profile Names=10-year,25-year,50-year,1pct_min,100-year,1pct_plu,500-year
River Rch & RM=Stream TC-1,Reach-1         ,6775
    2224    3942    5638    3890    7761   15485   14537
Boundary for River Rch & Prof#=Stream TC-1,Reach-1         , 1
Up Type= 0
Dn Type= 3
Dn Slope=0.01
Boundary for River Rch & Prof#=Stream TC-1,Reach-1         , 2
Up Type= 0
Dn Type= 3
Dn Slope=0.01
Boundary for River Rch & Prof#=Stream TC-1,Reach-1         , 3
Up Type= 0
Dn Type= 3
Dn Slope=0.01
Boundary for River Rch & Prof#=Stream TC-1,Reach-1         , 4
Up Type= 0
Dn Type= 3
Dn Slope=0.01
Boundary for River Rch & Prof#=Stream TC-1,Reach-1         , 5
Up Type= 0
Dn Type= 3
Dn Slope=0.01
Boundary for River Rch & Prof#=Stream TC-1,Reach-1         , 6
Up Type= 0
Dn Type= 3
Dn Slope=0.01
Boundary for River Rch & Prof#=Stream TC-1,Reach-1         , 7
Up Type= 0
Dn Type= 3
Dn Slope=0.01
DSS Import GetInterval= 0
DSS Import GetPeak= 0
DSS Import FillOption= 0

--- Stream TC-1.g01 (geometry) ---

Geom Title=Existing Conditions
Program Version=4.10

River Reach=Stream TC-1     ,Reach-1
Reach XY= 30
        1924725.       13943025.       1924768.1     13942975.14
      1924675.38     13942759.73      1924723.25     13942580.62
      1924632.83      13942478.4      1924674.01     13942414.36
      1924632.59     13942325.01      1924675.58     13942204.96
      1924621.24     13941976.56      1924419.41     13941530.61
      1924032.59     13941228.33      1924167.21     13941078.42
      1924075.38     13940859.73      1924120.01     13940672.45
      1923688.63     13940288.21      1923578.63      13940123.5
      1923567.14     13940018.83      1923002.14     13939351.16
      1922633.02     13939131.34      1922579.97     13938972.42
      1922734.83     13938914.48      1922805.81     13938804.96
      1922719.17     13938727.06      1922534.65      13938726.4
      1922439.09     13938774.77      1922222.42     13938669.29
      1922175.99     13938614.72      1922161.78     13938361.19
      1922093.53     13938324.62        1921975.       13938375.

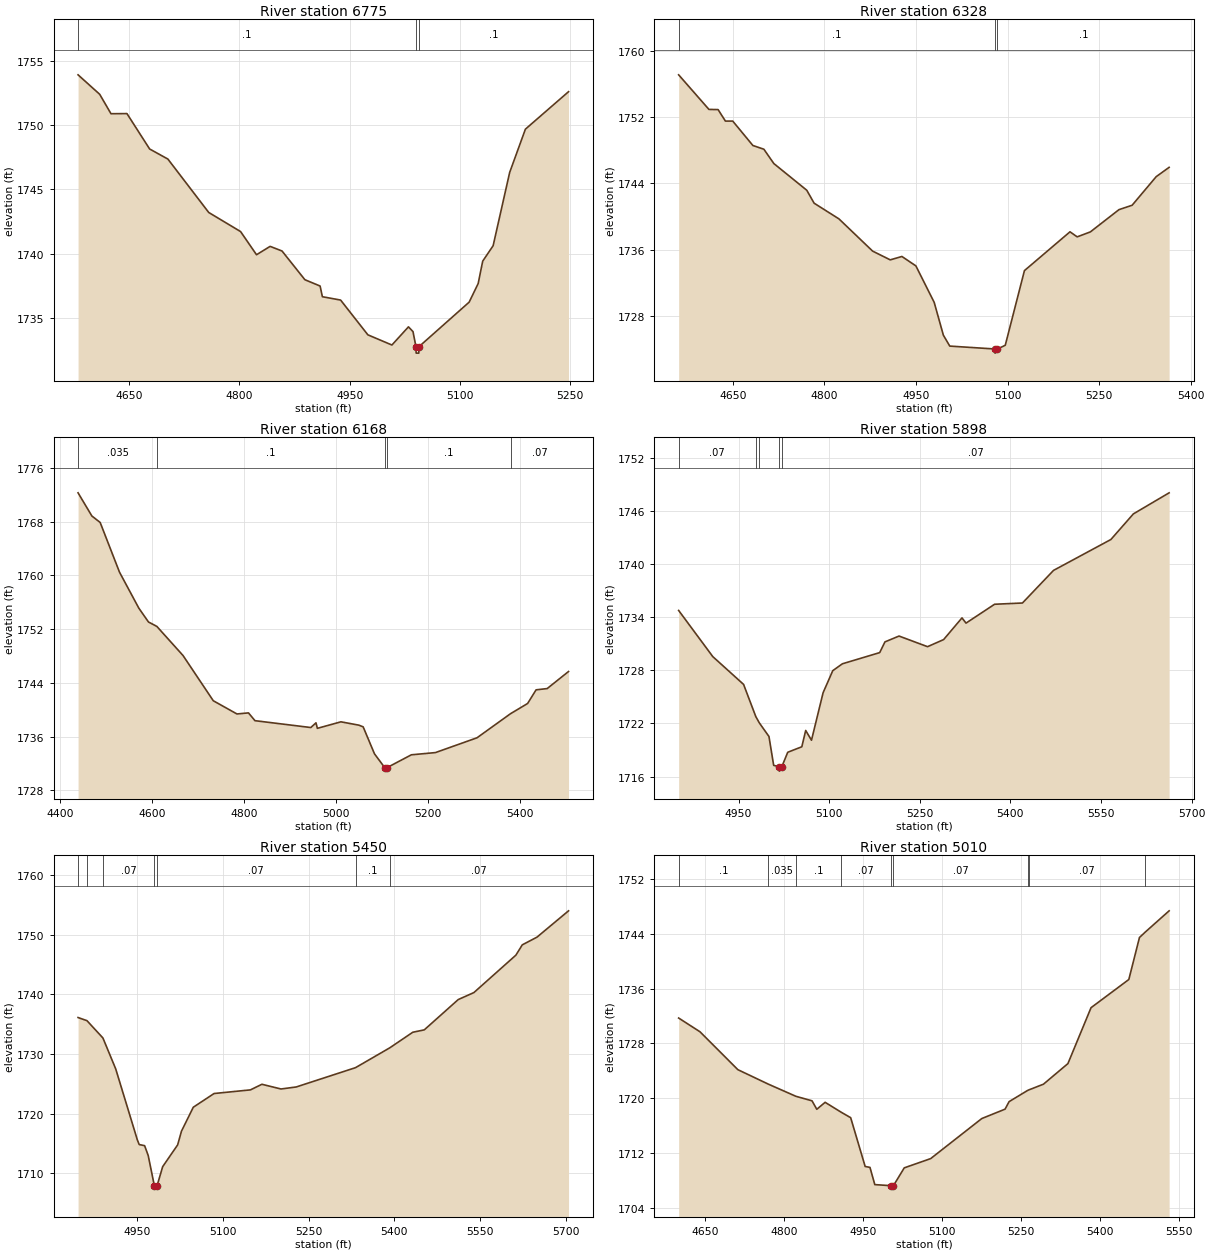
Type RM Length L Ch R = 1 ,6775    ,447,447,447
BEGIN DESCRIPTION:
Stream TC-1 13.0
END DESCRIPTION:
XS GIS Cut Line= 3
      1925175.02     13942874.99        1924775.       13942975.
      1924524.98       13943025.
#Sta/Elev= 30
  4580.5 1753.89  4609.9 1752.38  4625.3 1750.87    4647 1750.88  4677.9 1748.13
  4702.7 1747.35  4758.3  1743.2  4801.6 1741.72  4823.3 1739.92  4841.8 1740.57
    4858 1740.21  4889.1 1737.98  4909.8 1737.49  4912.9 1736.66  4937.7  1736.4
  4974.8  1733.7  5007.5 1732.91    5030 1734.32  5036.2 1733.95  5040.2 1732.78
  5040.5 1732.28  5044.1 1732.28  5044.3 1732.78  5112.6 1736.24  5124.9 1737.69
    5131 1739.42  5145.2 1740.62  5167.7 1746.31  5189.1 1749.67  5247.8 1752.58
#Mann= 3 ,-1 , 0
  4580.5      .1       0  5040.2     .05       0  5044.3      .1       0
Bank Sta=5040.2,5044.3
XS Rating Curve= 0 ,0
Exp/Cntr=0.3,0.1

Type RM Length L Ch R = 1 ,6328    ,160,160,160
BEGIN DESCRIPTION:
Stream TC-1 12.0
END DESCRIPTION:
XS GIS Cut Line= 3
      1925160.07     13942575.54        1924725.       13942575.
      1924417.95     13942778.43
#Sta/Elev= 30
  4561.3 1757.12  4610.9 1752.94  4625.9 1752.92  4637.9 1751.53  4649.9 1751.53
  4682.9 1748.58  4700.9 1748.13  4717.2  1746.4  4771.2 1743.17  4783.2 1741.61
  4823.9 1739.71    4879 1735.82  4907.9 1734.76    4927 1735.17  4949.9 1734.03
  4979.9 1729.62  4994.9 1725.66  5005.4 1724.34  5079.3 1723.99  5079.6 1723.49
  5083.5 1723.99  5096.3 1724.44  5127.7 1733.46  5202.3 1738.15  5214.1 1737.54
  5235.7 1738.14  5282.6 1740.83  5304.1 1741.36  5343.6 1744.82  5364.7 1745.94
#Mann= 3 ,-1 , 0
  4561.3      .1       0  5079.3     .05       0  5083.5      .1       0
Bank Sta=5079.3,5083.5
XS Rating Curve= 0 ,0
Exp/Cntr=0.3,0.1

Type RM Length L Ch R = 1 ,6168    ,270,270,270
BEGIN DESCRIPTION:
Stream TC-1 11.1
END DESCRIPTION:
XS GIS Cut Line= 5
      1925203.51     13942474.63      1924888.85     13942477.89
      1924671.83     13942458.36      1924589.37     13942451.85
      1924150.97     13942553.85
#Sta/Elev= 30
  4439.4 1772.29  4469.4 1768.84  4487.4 1767.88  4529.4 1760.48  4571.4 1755.12
  4592.4 1753.06  4610.6  1752.4  4667.4 1748.07  4733.1 1741.34  4784.5 1739.37
  4809.6 1739.53  4823.7 1738.37    4945 1737.35  4956.2 1738.05  4959.2 1737.23
  5010.4  1738.2  5049.5  1737.7  5058.7 1737.45  5083.3 1733.43  5105.8 1731.36
  5106.1 1730.86    5110 1731.36  5163.4 1733.29  5215.7 1733.62  5305.9 1735.82
  5378.8 1739.41  5415.9 1740.93  5434.3 1742.96  5458.4 1743.15  5504.8 1745.69
#Mann= 5 ,-1 , 0
  4439.4    .035       0  4610.6      .1       0  5105.8     .05       0
    5110      .1       0  5378.8     .07       0
Bank Sta=5105.8,5110
XS Rating Curve= 0 ,0
Exp/Cntr=0.3,0.1

Type RM Length L Ch R = 1 ,5898    ,448,448,448
BEGIN DESCRIPTION:
Stream TC-1 11.0
END DESCRIPTION:
XS GIS Cut Line= 4
      1924824.96       13942225.        1924675.       13942225.
      1924421.85     13942319.53      1924073.93      13942499.5
#Sta/Elev= 30
  4850.8 1734.75  4907.3 1729.54  4958.3  1726.4  4978.5 1722.77  4984.4 1722.05
  5000.3 1720.52  5008.1 1717.26  5017.3 1717.11  5017.6 1716.61  5021.6 1717.11
  5031.4 1718.74  5054.7 1719.36  5061.1  1721.2  5070.7  1720.1  5089.9 1725.46
  5105.9 1727.95  5121.9 1728.73  5183.6 1729.99  5192.3  1731.2  5215.6 1731.86
  5262.8 1730.66  5289.4 1731.46  5319.8 1733.91  5326.5 1733.32  5373.8 1735.45
  5419.9 1735.59  5471.3 1739.27  5566.3 1742.76  5603.5 1745.65  5662.7 1748.03
#Mann= 5 ,-1 , 0
  4850.8     .07       0  4978.5      .1       0  4984.4     .07       0
  5017.3     .05       0  5021.6     .07       0
Bank Sta=5017.3,5021.6
XS Rating Curve= 0 ,0
Exp/Cntr=0.3,0.1

Type RM Length L Ch R = 1 ,5450    ,440,440,440
BEGIN DESCRIPTION:
Stream TC-1 10.0
END DESCRIPTION:
XS GIS Cut Line= 4
      1924675.02     13941774.99        1924525.       13941825.
        1924425.       13941875.      1923896.92     13942134.88
#Sta/Elev= 30
  4846.4 1736.13    4862  1735.6  4889.9  1732.7  4912.3 1727.51  4950.2 1715.59
  4953.4 1714.82  4962.9 1714.63  4969.2 1712.97  4980.1 1707.84  4980.4 1707.34
  4984.5 1707.84  4994.5 1711.11  5020.7 1714.76  5027.4 1717.06  5048.1 1721.08
  5084.5 1723.38  5148.1 1723.99  5168.2 1724.93  5201.6 1724.14  5228.3 1724.48
  5332.1 1727.72  5391.9 1731.04  5432.3 1733.66  5452.4 1734.06  5511.8 1739.14
  5539.3 1740.32  5612.8  1746.6  5623.9 1748.32  5649.6 1749.61  5704.9 1754.03
#Mann= 7 ,-1 , 0
  4846.4    .035       0    4862      .1       0  4889.9     .07       0
  4980.1     .05       0  4984.5     .07       0  5332.1      .1       0
  5391.9     .07       0
Bank Sta=4980.1,4984.5
XS Rating Curve= 0 ,0
Exp/Cntr=0.3,0.1

Type RM Length L Ch R = 1 ,5010    ,341,341,341
BEGIN DESCRIPTION:
Stream TC-1 9.0
END DESCRIPTION:
XS GIS Cut Line= 3
      1924716.78     13941397.64        1924325.       13941475.
      1923924.96     13941825.03
#Sta/Elev= 30
  4600.5 1731.72    4641 1729.71  4712.9 1724.17  4770.9 1722.05    4823 1720.28
  4853.6 1719.62  4862.7 1718.38  4878.5  1719.4  4908.6 1717.97    4927 1717.15
  4954.5 1710.02  4963.6 1709.89  4972.8 1707.37  5003.7 1707.21    5004 1706.71
  5008.1 1707.21  5028.7 1709.82  5078.8 1711.17  5175.9 1717.03    5220  1718.4
  5227.7  1719.5  5262.7 1721.13  5264.7  1721.2  5292.9 1722.05  5339.3 1725.06
  5383.2 1733.23  5454.9 1737.35  5475.1 1743.49  5486.2 1744.29  5531.4 1747.39
#Mann= 9 ,-1 , 0
  4600.5      .1       0  4770.9    .035       0    4823      .1       0
  4908.6     .07       0  5003.7     .05       0  5008.1     .07       0
  5262.7    .035       0  5264.7     .07       0  5486.2    .035       0
Bank Sta=5003.7,5008.1
XS Rating Curve= 0 ,0
Exp/Cntr=0.3,0.1

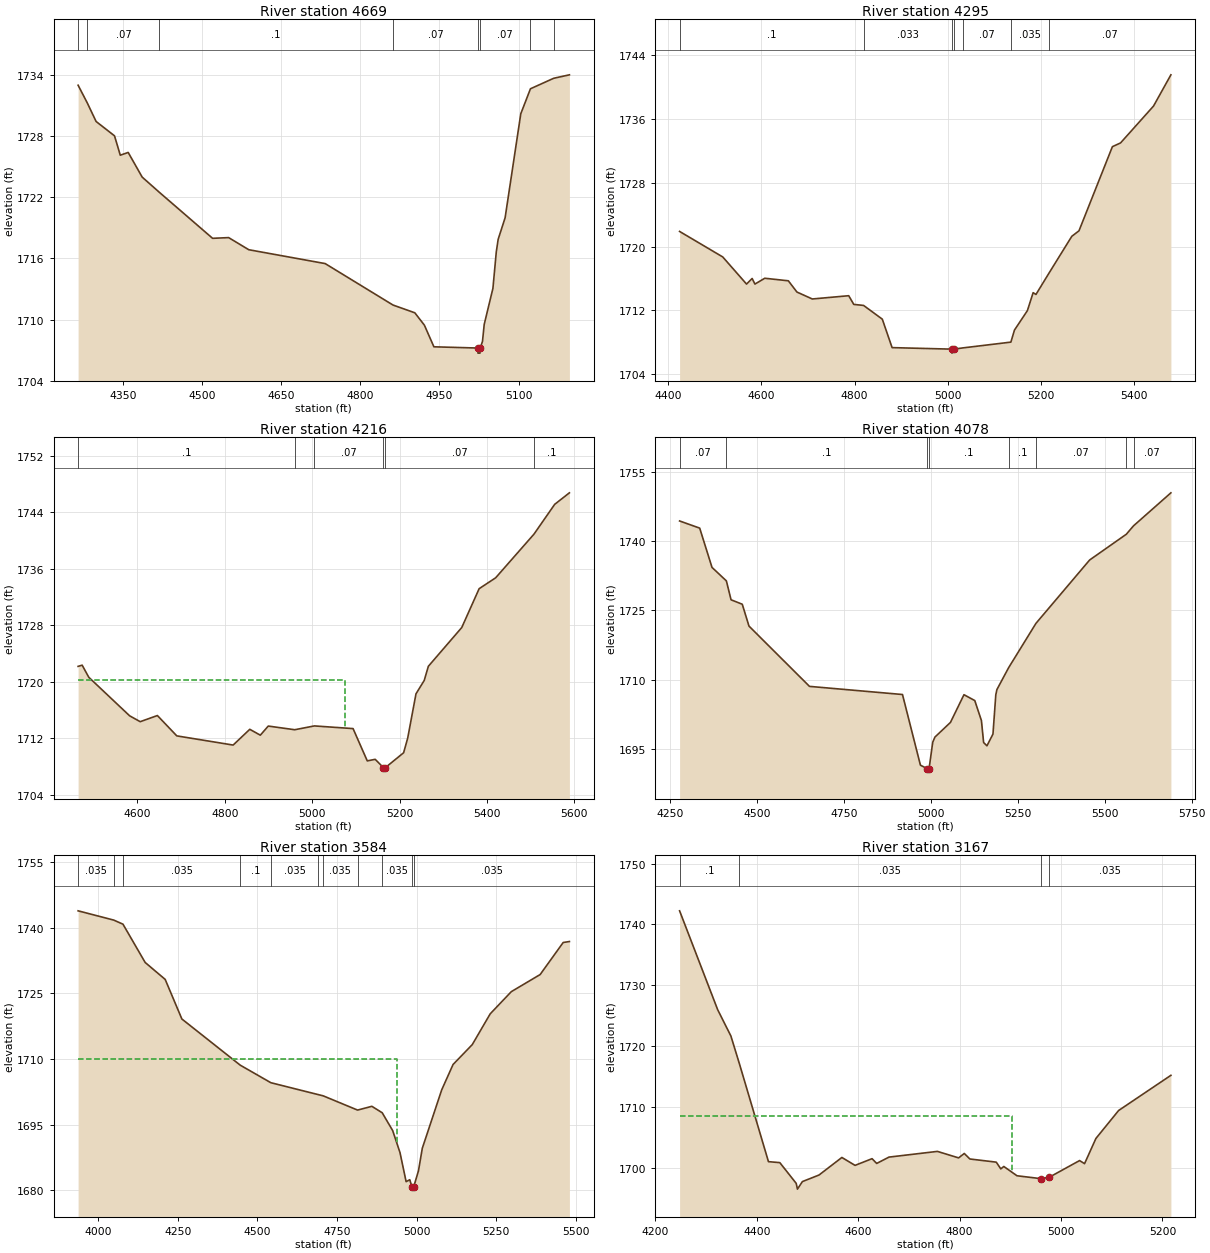
Type RM Length L Ch R = 1 ,4669    ,374,374,374
BEGIN DESCRIPTION:
Stream TC-1 8.0
END DESCRIPTION:
XS GIS Cut Line= 3
      1924790.93     13941313.99        1924115.     13941242.97
      1923886.89     13941348.06
#Sta/Elev= 30
  4265.5    1733  4282.8 1731.27  4299.6 1729.44  4334.5 1728.03  4345.4 1726.13
  4360.4  1726.4  4386.9 1723.98  4419.6 1722.48  4520.3 1717.97  4550.7 1718.04
  4588.9 1716.85  4733.6 1715.49  4862.1 1711.42  4903.4 1710.66  4921.5 1709.45
  4939.6 1707.32  5022.7  1707.2  5023.1  1706.7  5026.9  1706.7  5027.2  1707.2
  5031.6 1707.84  5034.9 1709.52  5051.4 1713.06  5057.8 1716.65  5061.3 1717.87
  5074.5 1719.99  5104.2  1730.2  5122.5 1732.65  5166.5 1733.68  5196.3 1734.02
#Mann= 8 ,-1 , 0
  4265.5    .035       0  4282.8     .07       0  4419.6      .1       0
  4862.1     .07       0  5022.7     .05       0  5027.2     .07       0
  5122.5    .035       0  5166.5     .07       0
Bank Sta=5022.7,5027.2
XS Rating Curve= 0 ,0
Exp/Cntr=0.3,0.1

Type RM Length L Ch R = 1 ,4295    ,79,79,79
BEGIN DESCRIPTION:
Stream TC_1 17.2
END DESCRIPTION:
XS GIS Cut Line= 3
        1924699.     13940966.75      1924164.96     13940964.13
      1923658.13     13941076.09
#Sta/Elev= 30
  4425.1  1721.9  4517.6  1718.7  4568.6  1715.3  4580.6    1716  4586.6  1715.3
  4607.7 1716.03  4658.2 1715.71  4676.6  1714.3  4709.6 1713.43  4787.6 1713.84
  4798.5 1712.75  4819.5 1712.62  4859.6  1710.9  4880.6 1707.33  5008.6 1707.14
  5008.9 1706.64  5013.1 1707.14  5031.6 1707.29  5135.2 1708.02  5142.9 1709.53
  5170.6 1711.97  5182.9 1714.22    5189    1714  5217.4 1716.72  5265.8 1721.29
  5281.2 1721.98  5352.8 1732.53  5370.3    1733  5440.9 1737.62  5478.2 1741.54
#Mann= 7 ,-1 , 0
  4425.1      .1       0  4819.5    .033       0  5008.6    .033       0
  5013.1    .033       0  5031.6     .07       0  5135.2    .035       0
  5217.4     .07       0
Bank Sta=5008.6,5013.1
XS Rating Curve= 0 ,0
Exp/Cntr=0.3,0.1

Type RM Length L Ch R = 1 ,4216    ,138,138,138
BEGIN DESCRIPTION:
Stream TC_1 17.0
END DESCRIPTION:
XS GIS Cut Line= 3
       1924633.7     13940838.12      1923936.29      13940921.4
       1923533.4     13941047.74
#Sta/Elev= 30
  4464.1 1722.18  4473.4 1722.35  4488.5 1720.64  4582.1 1715.18  4606.3 1714.35
  4645.6 1715.22    4690 1712.34    4819 1711.04  4857.1 1713.27  4881.2 1712.44
  4899.4 1713.73    4960 1713.21  5004.9 1713.75  5093.5 1713.37    5126  1708.8
  5144.1 1709.02    5163 1707.85  5163.3 1707.35  5167.5 1707.85  5209.2 1709.95
  5218.6 1712.04  5237.5 1718.29  5256.4 1720.19  5265.8 1722.19  5342.3 1727.68
  5382.1 1733.18  5419.9 1734.72  5507.6  1740.9    5555 1745.12  5588.7 1746.75
#Mann= 6 ,-1 , 0
  4464.1      .1       0    4960    .033       0  5004.9     .07       0
    5163    .033       0  5167.5     .07       0  5507.6      .1       0
#XS Ineff= 2 , 0
         5076.12 1720.26
Permanent Ineff=
       F       F
Bank Sta=5163,5167.5
XS Rating Curve= 0 ,0
Exp/Cntr=0.3,0.1

Type RM Length L Ch R = 1 ,4078    ,494,494,494
BEGIN DESCRIPTION:
Stream TC-1 7.0
END DESCRIPTION:
XS GIS Cut Line= 3
      1924753.29     13940509.24        1924075.       13940775.
      1923429.59     13941002.14
#Sta/Elev= 30
  4277.6 1744.37  4335.4 1742.82  4370.8 1734.32  4412.1  1731.4  4425.6 1727.31
  4457.8 1726.35  4477.1 1721.62  4651.1 1708.57  4918.5 1706.81  4970.1 1691.52
  4990.4 1690.73  4990.7 1690.23  4994.9 1690.73  5005.5 1696.49  5011.8  1697.6
  5056.4 1700.77  5095.3 1706.77  5126.4  1705.5  5145.5 1701.17  5151.8 1696.42
  5161.4 1695.71  5178.7 1698.26  5186.8 1706.73    5190 1707.88  5223.5 1712.59
  5302.3 1722.21  5456.6 1735.92    5562 1741.49  5582.9 1743.32  5690.3 1750.46
#Mann= 8 ,-1 , 0
  4277.6     .07       0  4412.1      .1       0  4990.4     .05       0
  4994.9      .1       0  5223.5      .1       0  5302.3     .07       0
    5562      .1       0  5582.9     .07       0
Bank Sta=4990.4,4994.9
XS Rating Curve= 0 ,0
Exp/Cntr=0.3,0.1

Type RM Length L Ch R = 1 ,3584    ,417,417,417
BEGIN DESCRIPTION:
Stream TC-1 6.0
END DESCRIPTION:
XS GIS Cut Line= 3
      1924501.03     13939606.38      1923838.09     13940435.41
       1923517.3     13940794.49
#Sta/Elev= 30
  3936.6 1743.82  4048.7  1741.7  4077.5 1740.77  4147.2 1732.03  4210.1 1728.16
  4262.5 1719.12  4445.9 1708.57    4542 1704.57  4691.5 1701.84  4706.4 1701.57
  4814.3 1698.32  4859.2 1699.18  4891.7 1697.71  4924.6 1693.63  4947.6  1688.6
  4966.8 1681.97  4978.2 1682.42  4985.2 1680.77  4985.6 1680.27  4990.5 1680.77
  5005.6 1684.46  5017.6  1689.6  5078.5 1702.93  5114.2 1708.73  5174.5 1713.27
  5230.8 1720.29  5297.1 1725.36  5387.7 1729.27  5460.1 1736.59  5479.6 1736.81
#Mann= 11 ,-1 , 0
  3936.6    .035       0  4048.7    .063       0  4077.5    .035       0
  4445.9      .1       0    4542    .035       0  4691.5     .07       0
  4706.4    .035       0  4814.3     .07       0  4891.7    .035       0
  4985.2    .035       0  4990.5    .035       0
#XS Ineff= 2 , 0
         4937.13  1709.9
Permanent Ineff=
       F       F
Bank Sta=4985.2,4990.5
XS Rating Curve= 0 ,0
Exp/Cntr=0.3,0.1

Type RM Length L Ch R = 1 ,3167    ,422,422,422
BEGIN DESCRIPTION:
Stream TC-1 5.0
END DESCRIPTION:
XS GIS Cut Line= 4
      1924021.15     13939513.31      1923709.56     13939940.51
        1923575.       13940125.      1923404.61     13940251.12
#Sta/Elev= 30
  4247.7 1742.25  4322.8 1725.98  4348.9 1721.65  4365.8 1717.05    4423 1700.97
  4445.4 1700.81  4477.7  1697.4  4480.2 1696.45  4489.9 1697.69  4522.7 1698.77
  4567.8 1701.66  4593.8 1700.36  4627.3 1701.46  4636.5 1700.68  4660.7 1701.72
  4756.2 1702.66  4798.1 1701.59  4809.2 1702.32  4820.3 1701.41  4872.3 1700.89
  4881.3 1699.78  4887.2 1700.18  4913.2 1698.65  4959.8 1698.18  4976.3 1698.38
  5036.7 1701.15  5046.5 1700.64  5068.9 1704.79  5113.7 1709.39  5216.8 1715.18
#Mann= 4 ,-1 , 0
  4247.7      .1       0  4365.8    .035       0  4959.8    .035       0
  4976.3    .035       0
#XS Ineff= 2 , 0
         4902.99 1708.44
Permanent Ineff=
       F       F
Bank Sta=4959.8,4976.3
XS Rating Curve= 0 ,0
Exp/Cntr=0.3,0.1

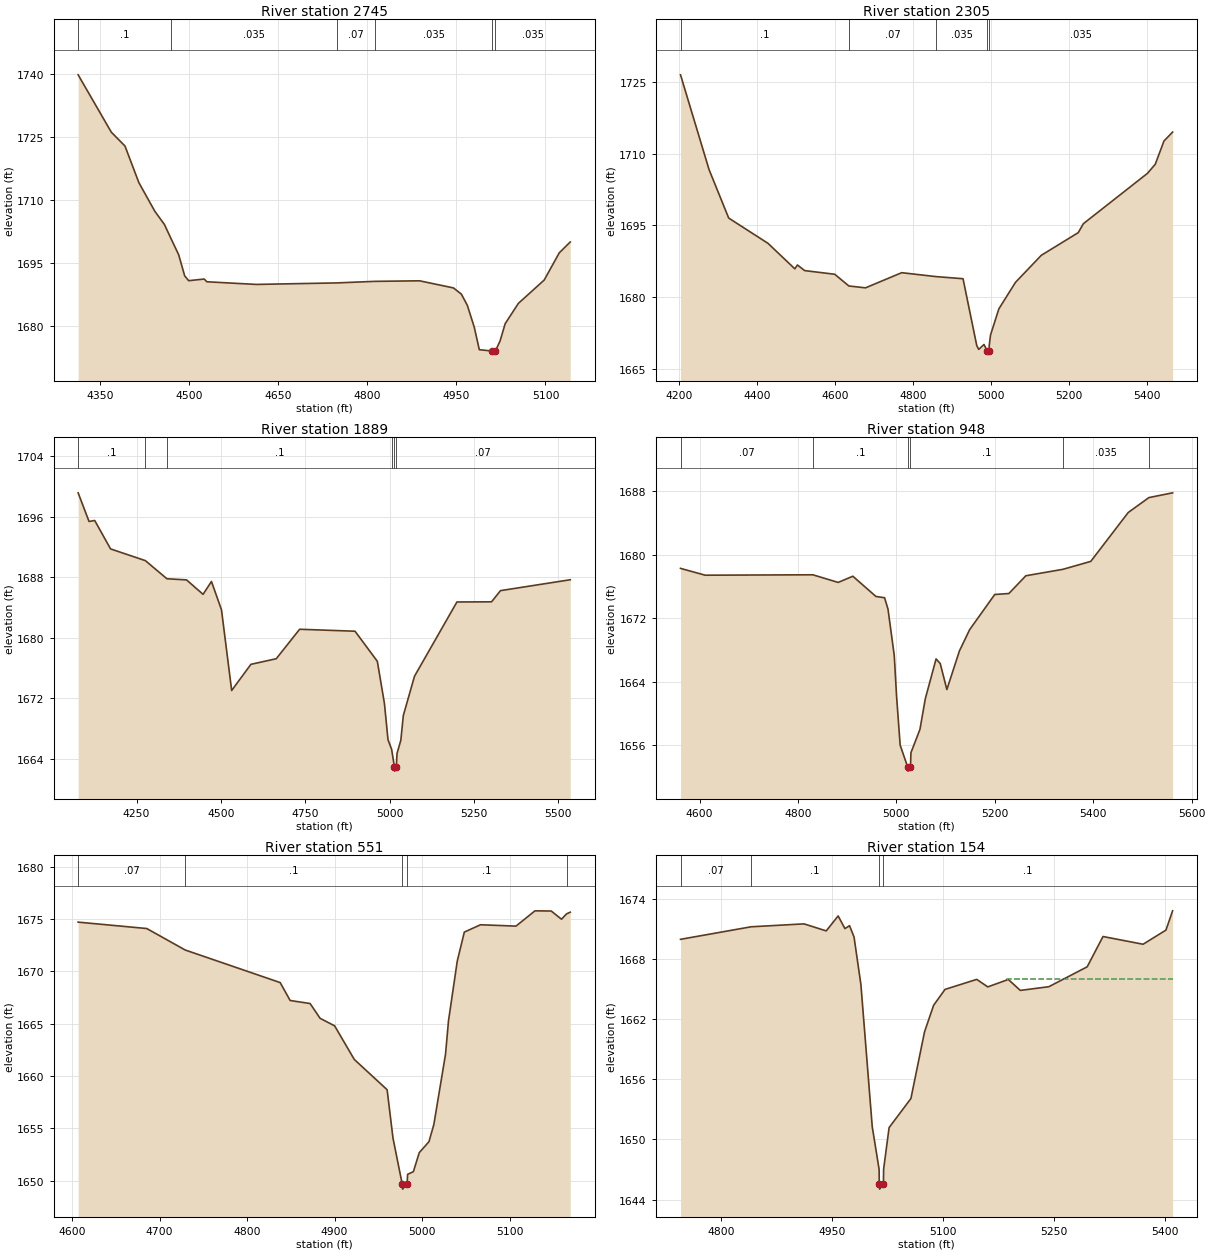
Type RM Length L Ch R = 1 ,2745    ,440,440,440
BEGIN DESCRIPTION:
Stream TC-1 4.0
END DESCRIPTION:
XS GIS Cut Line= 4
      1923990.04     13939467.48        1923475.       13939725.
        1923375.       13939775.      1923274.97     13939875.03
#Sta/Elev= 30
  4312.6 1739.78  4368.5 1726.13  4391.5 1722.84  4414.9 1714.13  4441.8 1707.31
    4458 1704.16  4468.8 1700.89    4482 1696.96  4492.1 1691.94  4498.8 1690.79
    4525 1691.18  4529.5 1690.53  4612.8  1689.9  4748.6 1690.26  4812.5 1690.63
  4887.9 1690.76  4944.9 1689.07  4958.3 1687.59  4968.4  1684.9    4980 1679.72
  4988.5 1674.36  5010.2 1674.05  5010.7 1673.55  5015.6 1674.05  5023.6 1676.49
    5032 1680.54  5054.3 1685.39  5097.8 1690.94  5123.2 1697.42  5141.7    1700
#Mann= 6 ,-1 , 0
  4312.6      .1       0  4468.8    .035       0  4748.6     .07       0
  4812.5    .035       0  5010.2    .035       0  5015.6    .035       0
Bank Sta=5010.2,5015.6
XS Rating Curve= 0 ,0
Exp/Cntr=0.3,0.1

Type RM Length L Ch R = 1 ,2305    ,416,416,416
BEGIN DESCRIPTION:
Stream TC-1 3.0
END DESCRIPTION:
XS GIS Cut Line= 4
      1923787.01       13939119.        1923175.       13939425.
        1923075.       13939475.      1922887.04     13939900.16
#Sta/Elev= 30
  4203.7 1726.47  4276.9 1706.63  4327.2  1696.5  4427.9 1691.21  4496.6 1685.88
  4503.3 1686.68  4521.8 1685.51  4598.9 1684.74  4635.1 1682.29  4677.7  1681.9
  4770.5 1685.07  4858.4 1684.25  4927.6 1683.81  4962.8 1669.81  4967.9 1669.02
  4981.3 1670.05  4989.2 1668.74  4989.6 1668.24  4994.6 1668.74  4994.7 1669.82
  4998.1 1672.05  5019.4  1677.5    5062 1683.05  5128.2 1688.71  5222.8 1693.45
  5235.9 1695.32  5399.9 1705.84  5420.1 1707.75  5442.5 1712.63  5464.6 1714.49
#Mann= 5 ,-1 , 0
  4203.7      .1       0  4635.1     .07       0  4858.4    .035       0
  4989.2    .035       0  4994.6    .035       0
Bank Sta=4989.2,4994.6
XS Rating Curve= 0 ,0
Exp/Cntr=0.3,0.1

Type RM Length L Ch R = 1 ,1889    ,941,941,941
BEGIN DESCRIPTION:
Stream TC-1 2.0
END DESCRIPTION:
XS GIS Cut Line= 4
      1923606.44     13938809.28        1922875.       13939175.
        1922775.       13939225.       1922551.6     13939704.32
#Sta/Elev= 30
  4076.8 1699.17  4109.1 1695.38  4125.9 1695.51  4172.9 1691.75    4276  1690.2
    4340  1687.8  4398.1 1687.65    4447 1685.74  4471.9 1687.44  4501.6  1683.7
  4531.8 1673.02  4588.8 1676.48  4663.9 1677.22  4733.2 1681.12  4897.4 1680.86
  4963.5 1676.88  4984.6 1671.28  4995.1 1666.51  5005.9 1665.23  5014.3 1662.85
  5014.7 1662.35  5019.7 1662.85  5021.8 1664.68  5033.1 1666.43  5040.5 1669.71
  5073.6  1674.9  5199.4 1684.73    5302 1684.75  5328.5 1686.23  5535.2 1687.67
#Mann= 6 ,-1 , 0
  4076.8      .1       0    4276     .07       0    4340      .1       0
  5005.9     .07       0  5014.3     .05       0  5019.7     .07       0
Bank Sta=5014.3,5019.7
XS Rating Curve= 0 ,0
Exp/Cntr=0.3,0.1

Type RM Length L Ch R = 1 ,948     ,397,397,397
BEGIN DESCRIPTION:
Stream TC-1 1.0
END DESCRIPTION:
XS GIS Cut Line= 4
      1922890.66     13938443.67      1922675.14     13938557.04
        1922575.       13938725.      1922255.88     13939186.18
#Sta/Elev= 30
  4561.4  1678.3  4611.5 1677.44  4830.4 1677.49  4881.7 1676.53  4911.6 1677.31
  4958.5 1674.76    4976  1674.6    4983 1673.17  4995.7 1667.33  5000.4 1662.21
  5007.7 1656.03  5023.1 1653.25  5023.6 1652.75  5028.7 1653.25  5029.6 1655.07
  5047.9 1658.01  5058.8 1661.87  5080.7 1666.89  5089.2  1666.3  5102.6 1663.03
  5128.1 1667.89  5148.9 1670.58  5199.9 1675.01  5228.6 1675.13  5263.1 1677.37
  5338.4 1678.18    5395 1679.18  5471.1 1685.34  5513.1 1687.22  5561.3 1687.82
#Mann= 6 ,-1 , 0
  4561.4     .07       0  4830.4      .1       0  5023.1     .05       0
  5028.7      .1       0  5338.4    .035       0  5513.1     .07       0
Bank Sta=5023.1,5028.7
XS Rating Curve= 0 ,0
Exp/Cntr=0.3,0.1

Type RM Length L Ch R = 1 ,551     ,397,397,397
BEGIN DESCRIPTION:
Stream_TC 0.0
END DESCRIPTION:
XS GIS Cut Line= 4
      1922496.83     13938397.86      1922274.92     13938570.15
       1922196.1     13938732.33      1922221.63     13938829.99
#Sta/Elev= 30
    4607 1674.69  4685.4 1674.08  4729.3 1672.03  4837.8 1668.92  4849.2 1667.21
    4872 1666.92  4883.4 1665.51    4900 1664.79  4922.5 1661.58    4960 1658.69
  4966.7 1654.07  4977.2  1649.7  4977.7  1649.2  4982.8  1649.7  4983.4 1650.61
    4990 1650.87  4996.7 1652.68  5007.8 1653.73  5013.4 1655.38  5026.7 1662.07
  5030.1 1665.26  5040.1 1670.96  5048.2 1673.74  5066.7 1674.44  5107.2 1674.31
  5128.9 1675.77  5147.5 1675.75  5159.2 1674.97    5165 1675.48  5169.2 1675.64
#Mann= 5 ,-1 , 0
    4607     .07       0  4729.3      .1       0  4977.2     .05       0
  4982.8      .1       0    5165     .07       0
Bank Sta=4977.2,4982.8
XS Rating Curve= 0 ,0
Exp/Cntr=0.3,0.1

Type RM Length L Ch R = 1 ,154     ,0,0,0
BEGIN DESCRIPTION:
Stream_TC 0.1
END DESCRIPTION:
XS GIS Cut Line= 3
      1922167.71     13938075.97      1922082.62     13938457.03
      1922129.85      13938727.8
#Sta/Elev= 30
  4744.7 1669.94  4840.2 1671.19  4911.7 1671.48  4941.7 1670.78  4957.8 1672.27
    4967 1671.01  4973.2  1671.3  4979.3 1670.18  4988.6 1665.43  5003.9 1651.28
  5013.2 1647.02  5013.4 1645.55  5013.9 1645.05    5019 1645.55  5019.3 1647.04
  5026.7 1651.18  5056.2 1654.08  5074.6 1660.72  5086.9 1663.37  5102.3 1664.95
  5145.2 1665.95  5160.1  1665.2  5187.9 1665.94  5204.1 1664.85  5242.7 1665.22
  5294.5  1667.2  5315.9 1670.22  5370.1 1669.45    5401 1670.86    5410 1672.78
#Mann= 4 ,-1 , 0
  4744.7     .07       0  4840.2      .1       0  5013.4     .05       0
    5019      .1       0
#XS Ineff= 2 , 0
                         5185.43         1665.96
Permanent Ineff=
       F       F
Bank Sta=5013.4,5019
XS Rating Curve= 0 ,0
Exp/Cntr=0.3,0.1

Chan Stop Cuts=-1
Use User Specified Reach Order=0
Composite Channel Slope=5