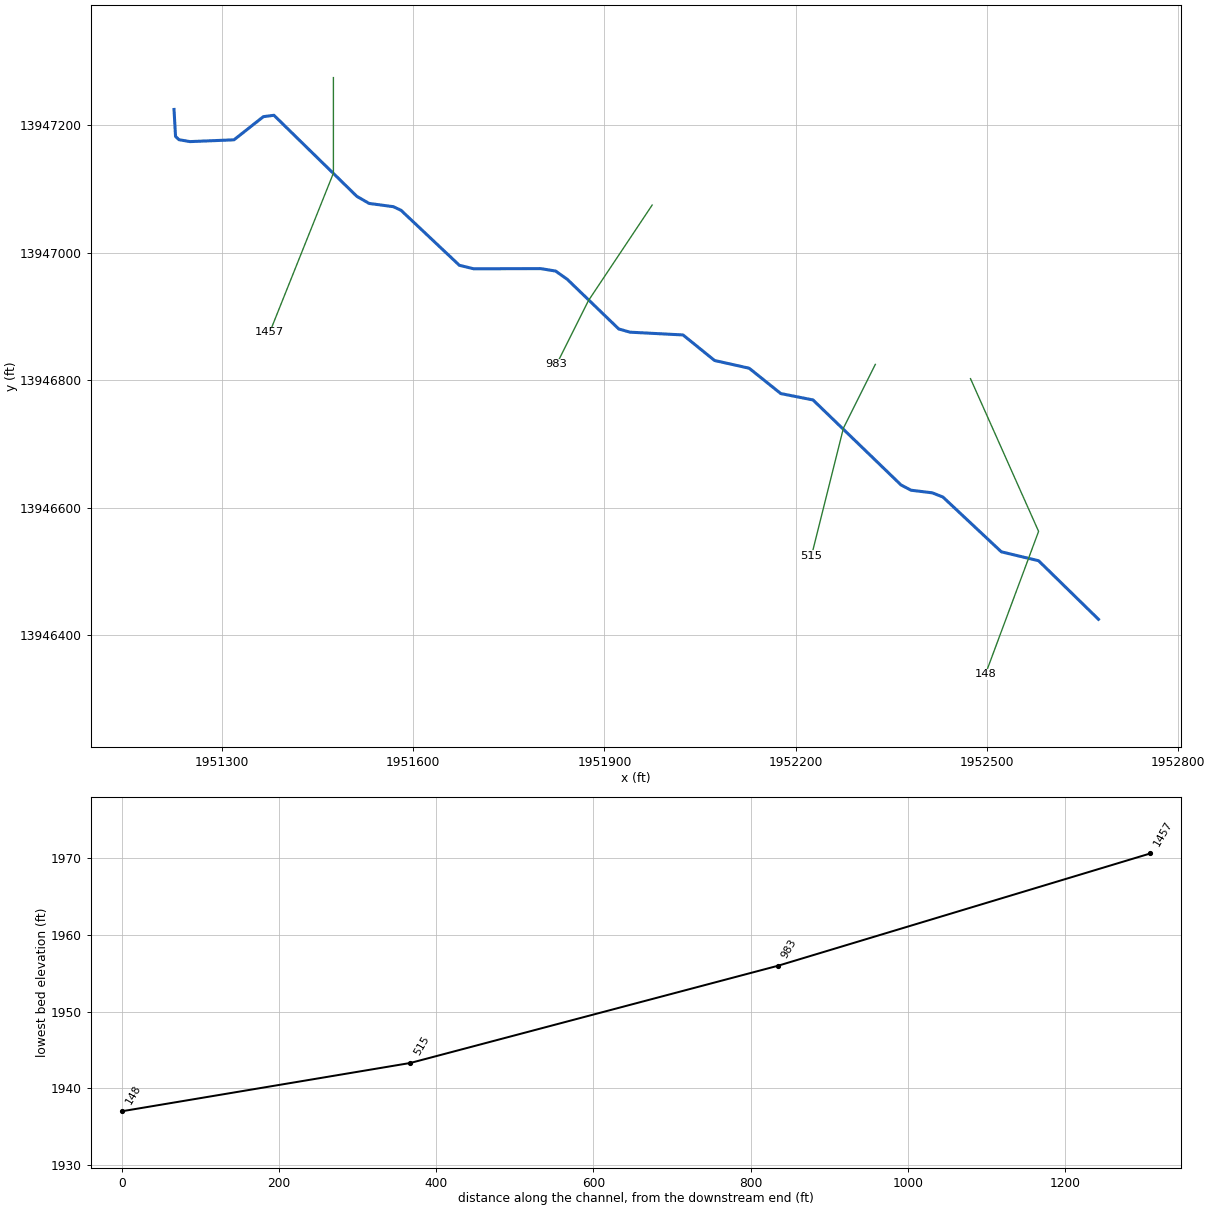
--- Stream0001.prj (project) ---

Proj Title=Stream0001 Base Level Engineering
Current Plan=p01
Default Exp/Contr=0.3,0.1
English Units
Geom File=g01
Flow File=f01
Plan File=p01
Y Axis Title=Elevation
X Axis Title(PF)=Main Channel Distance
X Axis Title(XS)=Station
BEGIN DESCRIPTION:
Stream0001
END DESCRIPTION:
DSS Export Rating Curves= 0
DSS Export Rating Curve Sorted= 0
DSS Export Volume Flow Curves= 0
DXF OffsetX= 0
DXF OffsetY= 0
DXF ScaleX= 1
DXF ScaleY= 10

--- Stream0001.p01 (plan) ---

Plan Title=Multiple Run
Short Identifier=Multiple
Geom File=g01
Flow File=f01
Subcritical Flow
K Sum by GR= 0
Std Step Tol= 0.01
Critical Tol= 0.01
Num of Std Step Trials= 20
Max Error Tol= 0.3
Flow Tol Ratio= 0.001
Split Flow NTrial= 30
Split Flow Tol= 0.02
Split Flow Ratio= 0.02
Log Output Level= 0
Friction Slope Method= 1
Unsteady Friction Slope Method= 2
Unsteady Bridges Friction Slope Method= 1
Parabolic Critical Depth
Global Vel Dist=  1 , 1 , 1
Global Log Level= 0
CheckData=True
Encroach Param= -1, 0, 0, 0
BEGIN DESCRIPTION:
Multiple Run
END DESCRIPTION:

--- Stream0001.f01 (steady flow) ---

Flow Title=Multiple
Program Version=4.10
Number of Profiles= 7
Profile Names=10-year,25-year,50-year,1pct_min,100-year,1pct_plu,500-year
River Rch & RM=Stream0001,Reach-1         ,1457
     707    1172    1604    1064    2123    4235    3662
Boundary for River Rch & Prof#=Stream0001,Reach-1         , 1
Up Type= 0
Dn Type= 3
Dn Slope=0.01
Boundary for River Rch & Prof#=Stream0001,Reach-1         , 2
Up Type= 0
Dn Type= 3
Dn Slope=0.01
Boundary for River Rch & Prof#=Stream0001,Reach-1         , 3
Up Type= 0
Dn Type= 3
Dn Slope=0.01
Boundary for River Rch & Prof#=Stream0001,Reach-1         , 4
Up Type= 0
Dn Type= 3
Dn Slope=0.01
Boundary for River Rch & Prof#=Stream0001,Reach-1         , 5
Up Type= 0
Dn Type= 3
Dn Slope=0.01
Boundary for River Rch & Prof#=Stream0001,Reach-1         , 6
Up Type= 0
Dn Type= 3
Dn Slope=0.01
Boundary for River Rch & Prof#=Stream0001,Reach-1         , 7
Up Type= 0
Dn Type= 3
Dn Slope=0.01
DSS Import GetInterval= 0
DSS Import GetPeak= 0
DSS Import FillOption= 0

--- Stream0001.g01 (geometry) ---

Geom Title=Existing Conditions
Program Version=4.10

River Reach=Stream0001      ,Reach-1
Reach XY= 30
        1951225.       13947225.      1951227.41     13947182.73
      1951232.76     13947177.57      1951249.92     13947174.55
      1951319.08     13947177.34      1951365.15     13947213.68
      1951381.74     13947215.87      1951511.79     13947088.63
      1951531.05     13947077.53      1951568.95     13947072.46
      1951581.04     13947066.82      1951672.56     13946980.48
      1951694.99     13946974.98      1951800.11     13946975.27
      1951823.53     13946971.44      1951841.75     13946958.53
      1951922.58     13946880.54      1951940.22     13946875.53
      1952023.41     13946871.17      1952072.82     13946831.12
       1952127.2     13946818.92      1952176.74     13946779.19
       1952227.3     13946769.17      1952365.32     13946635.78
      1952381.05     13946627.53      1952414.36     13946623.45
      1952431.04     13946616.82      1952522.71     13946530.86
      1952581.07     13946516.89        1952675.       13946425.

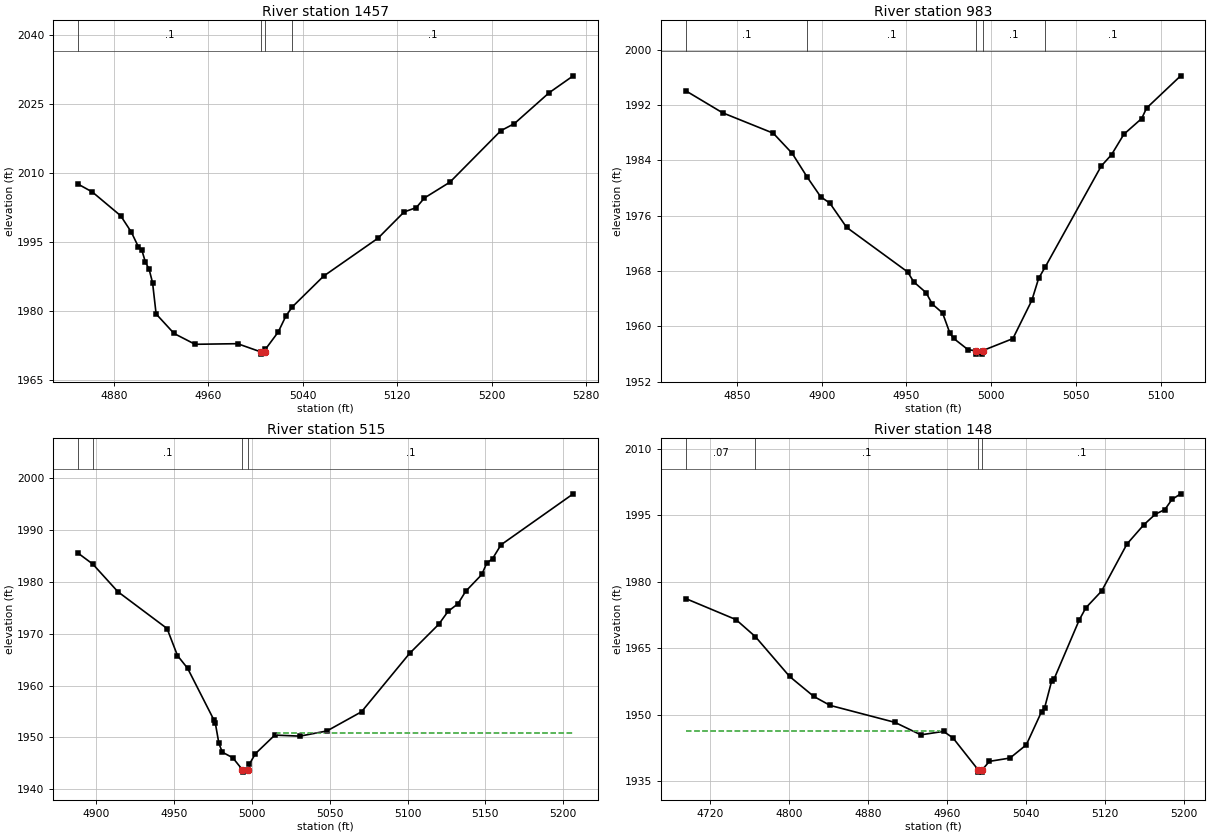
Type RM Length L Ch R = 1 ,1457    ,474,474,474
BEGIN DESCRIPTION:
Stream0001 3.0
END DESCRIPTION:
XS GIS Cut Line= 3
        1951475.     13947274.99        1951475.       13947125.
      1951375.02     13946875.04
#Sta/Elev= 30
  4849.8 2007.62  4861.8 2005.92  4885.8 2000.75  4894.8  1997.2  4900.8 1993.98
  4903.8 1993.21  4906.8  1990.6  4909.8 1989.18  4912.8 1986.18  4915.8 1979.39
    4931 1975.14  4948.8 1972.79  4984.8 1972.92  5004.3 1971.15  5004.5 1970.65
  5008.3 1971.15  5008.4 1971.72  5019.2 1975.46  5025.7 1978.94  5031.1 1980.92
  5057.6 1987.61  5103.8 1995.89  5125.8 2001.58  5136.1 2002.52    5143 2004.62
  5164.6 2008.06  5207.7 2019.25  5219.2  2020.8  5248.6 2027.51    5269 2031.19
#Mann= 4 ,-1 , 0
  4849.8      .1       0  5004.3     .05       0  5008.3      .1       0
  5031.1      .1       0
Bank Sta=5004.3,5008.3
XS Rating Curve= 0 ,0
Exp/Cntr=0.3,0.1

Type RM Length L Ch R = 1 ,983     ,468,468,468
BEGIN DESCRIPTION:
Stream0001 2.0
END DESCRIPTION:
XS GIS Cut Line= 3
      1951975.01     13947075.01        1951875.       13946925.
        1951825.       13946825.
#Sta/Elev= 30
  4819.7 1994.06  4841.5 1990.87  4871.4 1987.92  4882.6    1985  4891.5 1981.55
  4899.4 1978.73  4904.8 1977.81  4914.7 1974.31  4950.7 1967.87  4954.3 1966.43
  4961.6 1964.87  4965.2 1963.24  4971.3 1961.94  4975.6 1959.05  4977.8 1958.27
  4986.4 1956.62  4990.9 1956.49  4991.2 1955.99  4994.7 1955.99  4994.9 1956.49
  5012.8 1958.23    5024 1963.77    5028 1966.94  5031.9 1968.59  5064.9 1983.16
    5071 1984.81  5078.3 1987.77  5088.8 1990.04  5091.7 1991.55  5111.8 1996.21
#Mann= 5 ,-1 , 0
  4819.7      .1       0  4891.5      .1       0  4990.9     .05       0
  4994.9      .1       0  5031.9      .1       0
Bank Sta=4990.9,4994.9
XS Rating Curve= 0 ,0
Exp/Cntr=0.3,0.1

Type RM Length L Ch R = 1 ,515     ,367,367,367
BEGIN DESCRIPTION:
Stream0001 1.0
END DESCRIPTION:
XS GIS Cut Line= 3
      1952325.02     13946825.03        1952275.       13946725.
        1952225.       13946525.
#Sta/Elev= 30
  4888.4 1985.57  4897.8 1983.47  4913.9 1978.14  4945.5 1971.03  4952.2  1965.8
  4958.7 1963.35  4975.7 1953.31  4976.5 1952.77  4978.8 1948.84    4981 1947.15
  4987.7 1946.08  4993.8  1943.8    4994  1943.3  4997.8  1943.8  4998.4 1944.85
  5002.3 1946.88  5014.7 1950.45  5030.9 1950.25  5048.2 1951.25  5070.4 1954.95
  5101.3 1966.23    5120 1971.84    5126 1974.34  5132.4 1975.82  5137.3 1978.21
  5147.7 1981.47  5150.8 1983.63  5154.6 1984.53    5160 1987.19  5206.4 1997.04
#Mann= 4 ,-1 , 0
  4888.4     .07       0  4897.8      .1       0  4993.8     .05       0
  4997.8      .1       0
#XS Ineff= 2 , 0
                         5015.83         1950.78
Permanent Ineff=
       F       F
Bank Sta=4993.8,4997.8
XS Rating Curve= 0 ,0
Exp/Cntr=0.3,0.1

Type RM Length L Ch R = 1 ,148     ,0,0,0
BEGIN DESCRIPTION:
Stream0001 5.0
END DESCRIPTION:
XS GIS Cut Line= 3
      1952474.31     13946802.57      1952581.09     13946562.96
      1952497.76     13946338.99
#Sta/Elev= 30
  4695.1  1976.2  4746.1 1971.44  4765.7  1967.6  4800.4  1958.6  4824.9 1954.09
  4841.4 1952.07    4907 1948.24  4933.3 1945.42  4956.3  1946.2  4965.9 1944.71
  4991.4  1937.5  4991.6    1937  4995.1    1937  4995.4  1937.5  5002.7 1939.43
  5023.6 1940.18  5040.1 1943.16  5055.6 1950.68  5058.7 1951.57  5065.7 1957.53
  5068.4 1958.12  5093.7 1971.36  5100.4 1974.11  5116.4  1977.9    5142  1988.5
    5159 1992.83  5170.7 1995.23  5180.4 1996.29  5187.6 1998.57  5196.4 1999.84
#Mann= 4 ,-1 , 0
  4695.1     .07       0  4765.7      .1       0  4991.4     .05       0
  4995.4      .1       0
#XS Ineff= 2 , 0
         4952.45 1946.21
Permanent Ineff=
       F       F
Bank Sta=4991.4,4995.4
XS Rating Curve= 0 ,0
Exp/Cntr=0.3,0.1

Chan Stop Cuts=-1
Use User Specified Reach Order=0
Composite Channel Slope=5