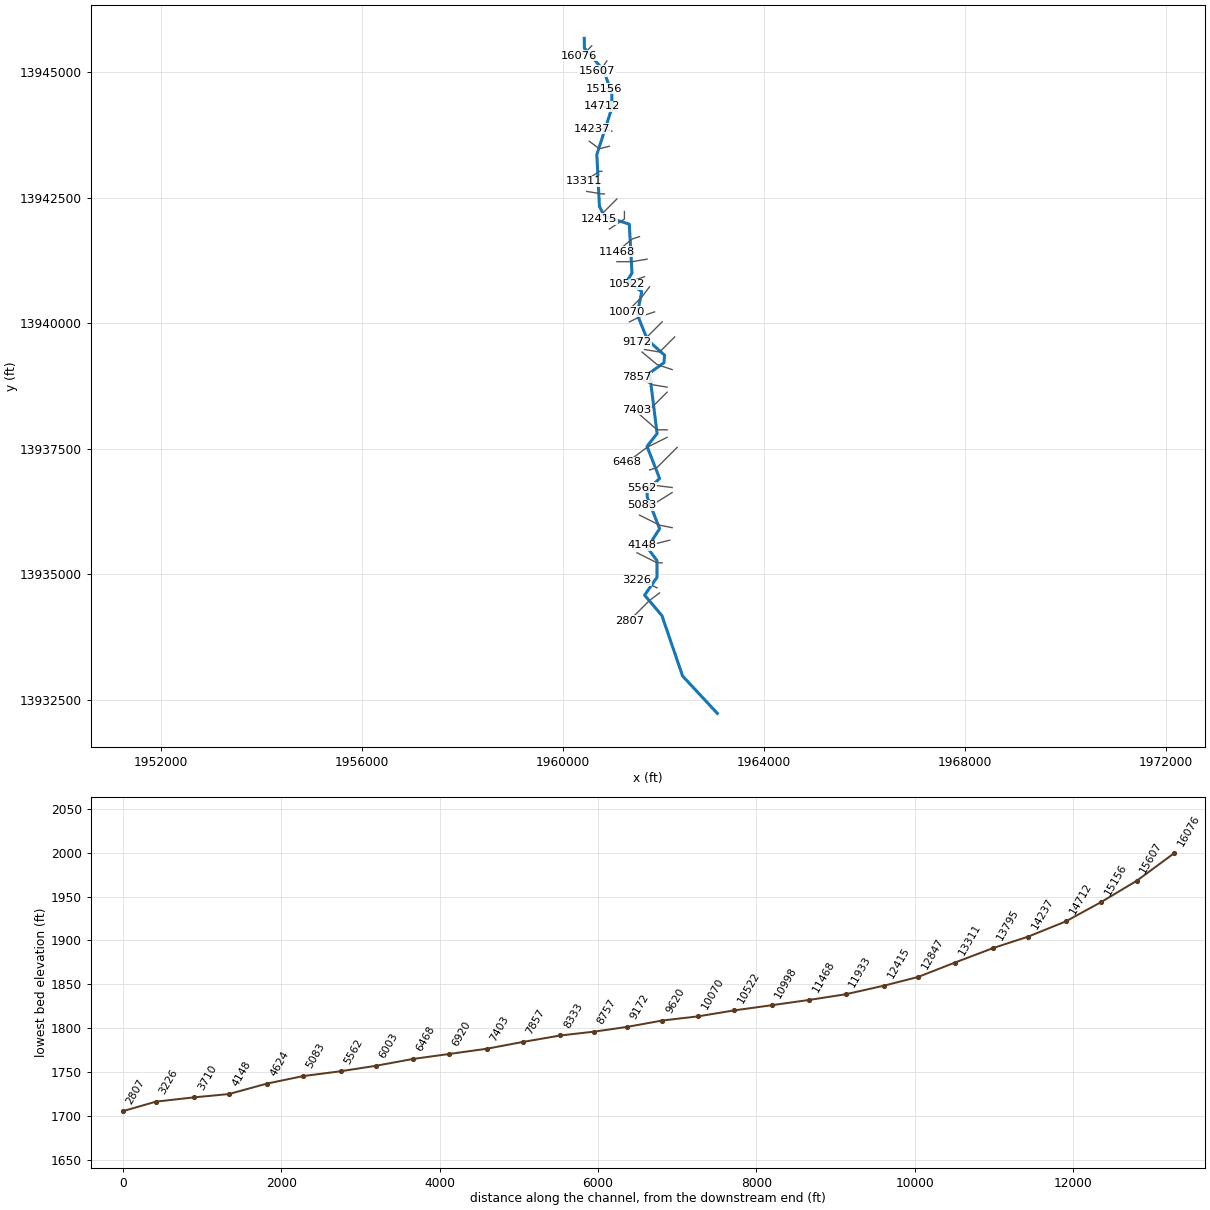
--- Stream0002.prj (project) ---

Proj Title=Stream0002 Base Level Engineering
Current Plan=p01
Default Exp/Contr=0.3,0.1
English Units
Geom File=g01
Flow File=f01
Plan File=p01
Y Axis Title=Elevation
X Axis Title(PF)=Main Channel Distance
X Axis Title(XS)=Station
BEGIN DESCRIPTION:
Stream0002
END DESCRIPTION:
DSS Export Rating Curves= 0
DSS Export Rating Curve Sorted= 0
DSS Export Volume Flow Curves= 0
DXF OffsetX= 0
DXF OffsetY= 0
DXF ScaleX= 1
DXF ScaleY= 10

--- Stream0002.p01 (plan) ---

Plan Title=Multiple Run
Short Identifier=Multiple
Geom File=g01
Flow File=f01
Subcritical Flow
K Sum by GR= 0
Std Step Tol= 0.01
Critical Tol= 0.01
Num of Std Step Trials= 20
Max Error Tol= 0.3
Flow Tol Ratio= 0.001
Split Flow NTrial= 30
Split Flow Tol= 0.02
Split Flow Ratio= 0.02
Log Output Level= 0
Friction Slope Method= 1
Unsteady Friction Slope Method= 2
Unsteady Bridges Friction Slope Method= 1
Parabolic Critical Depth
Global Vel Dist=  1 , 1 , 1
Global Log Level= 0
CheckData=True
Encroach Param= -1, 0, 0, 0
BEGIN DESCRIPTION:
Multiple Run
END DESCRIPTION:

--- Stream0002.f01 (steady flow) ---

Flow Title=Multiple
Program Version=4.10
Number of Profiles= 7
Profile Names=10-year,25-year,50-year,1pct_min,100-year,1pct_plu,500-year
River Rch & RM=Stream0002,Reach-1         ,16076
     171     255     325     203     404     807     612
River Rch & RM=Stream0002,Reach-1         ,15156
     423     680     912     595    1187    2369    1978
River Rch & RM=Stream0002,Reach-1         ,13795
    1239    2141    3014    2054    4097    8175    7472
River Rch & RM=Stream0002,Reach-1         ,10998
    1739    3042    4315    2958    5902   11776   10899
River Rch & RM=Stream0002,Reach-1         ,6920
    2056    3622    5161    3551    7084   14135   13182
River Rch & RM=Stream0002,Reach-1         ,2807
    2354    4172    5969    4120    8220   16401   15399
Boundary for River Rch & Prof#=Stream0002,Reach-1         , 1
Up Type= 0
Dn Type= 3
Dn Slope=0.008
Boundary for River Rch & Prof#=Stream0002,Reach-1         , 2
Up Type= 0
Dn Type= 3
Dn Slope=0.008
Boundary for River Rch & Prof#=Stream0002,Reach-1         , 3
Up Type= 0
Dn Type= 3
Dn Slope=0.008
Boundary for River Rch & Prof#=Stream0002,Reach-1         , 4
Up Type= 0
Dn Type= 3
Dn Slope=0.008
Boundary for River Rch & Prof#=Stream0002,Reach-1         , 5
Up Type= 0
Dn Type= 3
Dn Slope=0.008
Boundary for River Rch & Prof#=Stream0002,Reach-1         , 6
Up Type= 0
Dn Type= 3
Dn Slope=0.008
Boundary for River Rch & Prof#=Stream0002,Reach-1         , 7
Up Type= 0
Dn Type= 3
Dn Slope=0.008
DSS Import GetInterval= 0
DSS Import GetPeak= 0
DSS Import FillOption= 0

--- Stream0002.g01 (geometry) ---

Geom Title=Existing Conditions
Program Version=4.10

River Reach=Stream0002      ,Reach-1
Reach XY= 30
        1960425.       13945675.      1960428.53     13945476.46
      1960819.48     13945027.43      1960975.09      13944554.9
      1960973.02      13944280.9      1960675.51     13943359.79
      1960727.17     13942330.97      1960822.29      13942130.4
      1961321.47     13941973.55      1961375.29     13940999.88
      1961276.14     13940837.04      1961569.66     13940627.73
      1961478.67     13940176.58      1961683.16     13939668.95
      1962024.69     13939359.96      1962011.81     13939211.27
      1961724.96     13939005.02      1961875.33     13937799.79
      1961674.89      13937545.1      1961925.47     13936904.83
       1961682.8     13936681.21      1961675.04     13936545.03
      1961925.39     13935904.87      1961682.28     13935525.09
      1961872.94     13935269.15       1961873.8      13934935.5
      1961626.67     13934581.13      1961971.25     13934173.44
      1962383.14     13932968.94        1963075.       13932225.

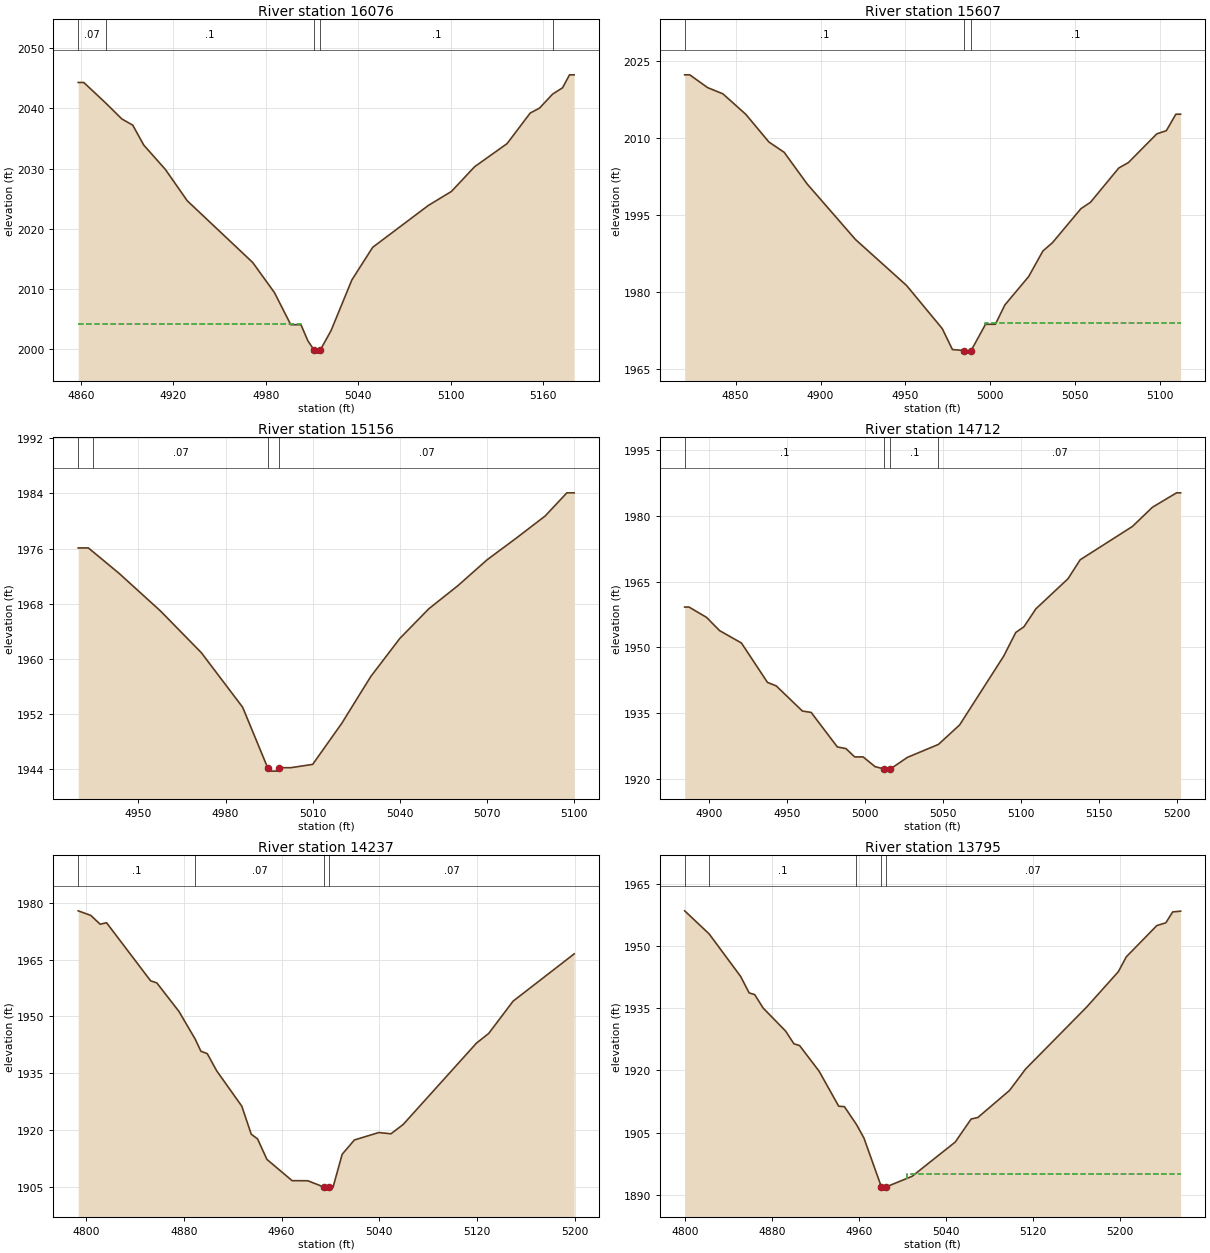
Type RM Length L Ch R = 1 ,16076   ,469,469,469
BEGIN DESCRIPTION:
Stream0002 35.0
END DESCRIPTION:
XS GIS Cut Line= 3
      1960575.02     13945525.02        1960475.       13945425.
      1960325.02     13945325.01
#Sta/Elev= 30
  4858.3 2044.32  4861.9 2044.32    4876 2040.94  4886.6 2038.26  4893.7 2037.22
  4900.8 2033.92  4914.9 2029.85    4929 2024.67  4971.5  2014.4  4985.6  2009.4
  4996.2 2004.06  5002.8 2004.06  5007.3 2001.38  5011.3 1999.84  5011.5 1999.34
    5015 1999.34  5015.3 1999.84  5022.3 2003.08  5035.8  2011.5  5049.3 2016.92
  5085.4 2023.88  5100.4 2026.21  5115.4 2030.31  5136.5 2034.16  5151.5 2039.24
  5157.5 2040.05    5166 2042.38  5172.5 2043.44    5177 2045.59    5180 2045.59
#Mann= 5 ,-1 , 0
  4858.3     .07       0    4876      .1       0  5011.3     .05       0
  5015.3      .1       0    5166    .035       0
#XS Ineff= 2 , 0
          5002.7 2004.26
Permanent Ineff=
       F       F
Bank Sta=5011.3,5015.3
XS Rating Curve= 0 ,0
Exp/Cntr=0.3,0.1

Type RM Length L Ch R = 1 ,15607   ,451,451,451
BEGIN DESCRIPTION:
Stream0002 34.0
END DESCRIPTION:
XS GIS Cut Line= 3
      1960874.99     13945224.98        1960775.       13945075.
      1960674.96     13945024.98
#Sta/Elev= 30
    4820 2022.27    4823 2022.27  4833.5 2019.78  4842.5 2018.57    4856 2014.58
  4869.6 2009.19  4878.6 2007.18  4892.1 2001.03  4920.6  1990.2  4950.7 1981.24
  4971.7 1972.85  4977.7 1968.77  4984.7 1968.57    4985 1968.07  4988.5 1968.07
  4988.7 1968.57  4997.2 1973.69    5003 1973.69  5008.6 1977.46  5022.6 1982.98
    5031 1987.97  5036.6 1989.57  5053.4 1996.21    5059 1997.44  5075.7 2004.13
  5081.3 2005.17  5098.1 2010.78  5103.7 2011.39  5109.3  2014.6  5112.1  2014.6
#Mann= 3 ,-1 , 0
    4820      .1       0  4984.7     .05       0  4988.7      .1       0
#XS Ineff= 2 , 0
                         4996.85         1973.97
Permanent Ineff=
       F       F
Bank Sta=4984.7,4988.7
XS Rating Curve= 0 ,0
Exp/Cntr=0.3,0.1

Type RM Length L Ch R = 1 ,15156   ,444,444,444
BEGIN DESCRIPTION:
Stream0002 33.0
END DESCRIPTION:
XS GIS Cut Line= 3
      1960974.99     13944724.99        1960925.       13944675.
        1960825.       13944675.
#Sta/Elev= 24
  4929.3 1976.09  4932.8 1976.09  4934.5  1975.5  4943.4 1972.39  4957.6 1966.95
  4971.7 1960.88  4985.9 1952.97  4994.5  1944.2  4994.7  1943.7  4998.2  1943.7
  4998.5  1944.2    5000  1944.2  5002.5  1944.2    5010 1944.68    5020 1950.63
    5030 1957.43    5040 1962.96    5050 1967.27    5060 1970.62    5070 1974.36
    5080 1977.49    5090 1980.72  5097.5 1984.09    5100 1984.09
#Mann= 4 ,-1 , 0
  4929.3      .1       0  4934.5     .07       0  4994.5     .05       0
  4998.5     .07       0
Bank Sta=4994.5,4998.5
XS Rating Curve= 0 ,0
Exp/Cntr=0.3,0.1

Type RM Length L Ch R = 1 ,14712   ,475,475,475
BEGIN DESCRIPTION:
Stream0002 32.0
END DESCRIPTION:
XS GIS Cut Line= 3
      1961075.02     13944224.99        1960975.       13944275.
      1960774.99       13944325.
#Sta/Elev= 30
  4884.3 1959.23  4887.1 1959.23  4898.3 1956.88  4906.7 1953.85  4920.7 1951.02
  4937.4 1942.02    4943 1941.23  4959.8 1935.48  4965.4 1935.17  4982.2 1927.28
  4987.7 1926.91  4993.3 1925.01  4998.7 1925.01  5006.4 1922.78  5012.2 1922.26
  5012.4 1921.76  5016.2 1922.26  5027.1  1924.9    5047 1927.86  5060.6 1932.31
  5088.9 1948.05  5096.6 1953.43  5101.8 1954.71  5109.5 1958.83  5130.1  1965.7
  5137.9 1970.03  5171.4 1977.64  5184.2 1982.02  5199.7 1985.32  5202.3 1985.32
#Mann= 4 ,-1 , 0
  4884.3      .1       0  5012.2     .05       0  5016.2      .1       0
    5047     .07       0
Bank Sta=5012.2,5016.2
XS Rating Curve= 0 ,0
Exp/Cntr=0.3,0.1

Type RM Length L Ch R = 1 ,14237   ,442,442,442
BEGIN DESCRIPTION:
Stream0002 31.0
END DESCRIPTION:
XS GIS Cut Line= 3
      1960975.01       13943825.        1960775.       13943875.
      1960574.96       13943875.
#Sta/Elev= 30
  4793.4 1977.92  4803.7 1976.71  4811.4 1974.38  4816.6 1974.78  4852.7 1959.43
  4857.8 1958.87  4875.9 1951.34  4889.2 1944.03  4893.9 1940.81  4899.1 1940.18
  4906.8 1935.65  4927.4 1926.29  4935.1  1918.9  4940.3 1917.64    4948 1912.21
  4968.6 1906.61  4981.5 1906.58    4995 1904.87  4995.2 1904.37    4999 1904.87
  5002.1 1904.87  5009.6 1913.58  5019.6 1917.36  5039.6 1919.33  5049.6    1919
  5059.6 1921.47  5119.6 1942.96  5129.6 1945.51  5149.6 1954.05  5199.6 1966.54
#Mann= 4 ,-1 , 0
  4793.4      .1       0  4889.2     .07       0    4995     .05       0
    4999     .07       0
Bank Sta=4995,4999
XS Rating Curve= 0 ,0
Exp/Cntr=0.3,0.1

Type RM Length L Ch R = 1 ,13795   ,484,484,484
BEGIN DESCRIPTION:
Stream0002 30.0
END DESCRIPTION:
XS GIS Cut Line= 3
      1960925.01       13943525.        1960725.       13943475.
      1960524.97     13943625.02
#Sta/Elev= 30
  4799.8 1958.54  4822.3 1952.97  4851.3 1942.69  4859.1 1938.72  4864.2 1938.32
    4872 1935.06  4892.6 1929.52  4900.3 1926.43  4905.5 1926.01  4923.5  1919.8
  4941.5 1911.36  4946.7 1911.26  4957.8 1906.96  4964.7 1903.68  4980.8 1891.84
    4981 1891.34  4984.8 1891.84  5009.1 1894.45  5048.7 1902.71  5063.3 1908.27
  5069.5 1908.64  5098.7 1915.19  5113.3 1920.32  5169.5 1935.28  5198.7 1943.84
    5206 1947.42  5234.1 1954.98  5242.4 1955.65  5248.7 1958.28    5256 1958.46
#Mann= 5 ,-1 , 0
  4799.8     .07       0  4822.3      .1       0  4957.8     .07       0
  4980.8     .05       0  4984.8     .07       0
#XS Ineff= 2 , 0
                          5003.9         1895.03
Permanent Ineff=
       F       F
Bank Sta=4980.8,4984.8
XS Rating Curve= 0 ,0
Exp/Cntr=0.3,0.1

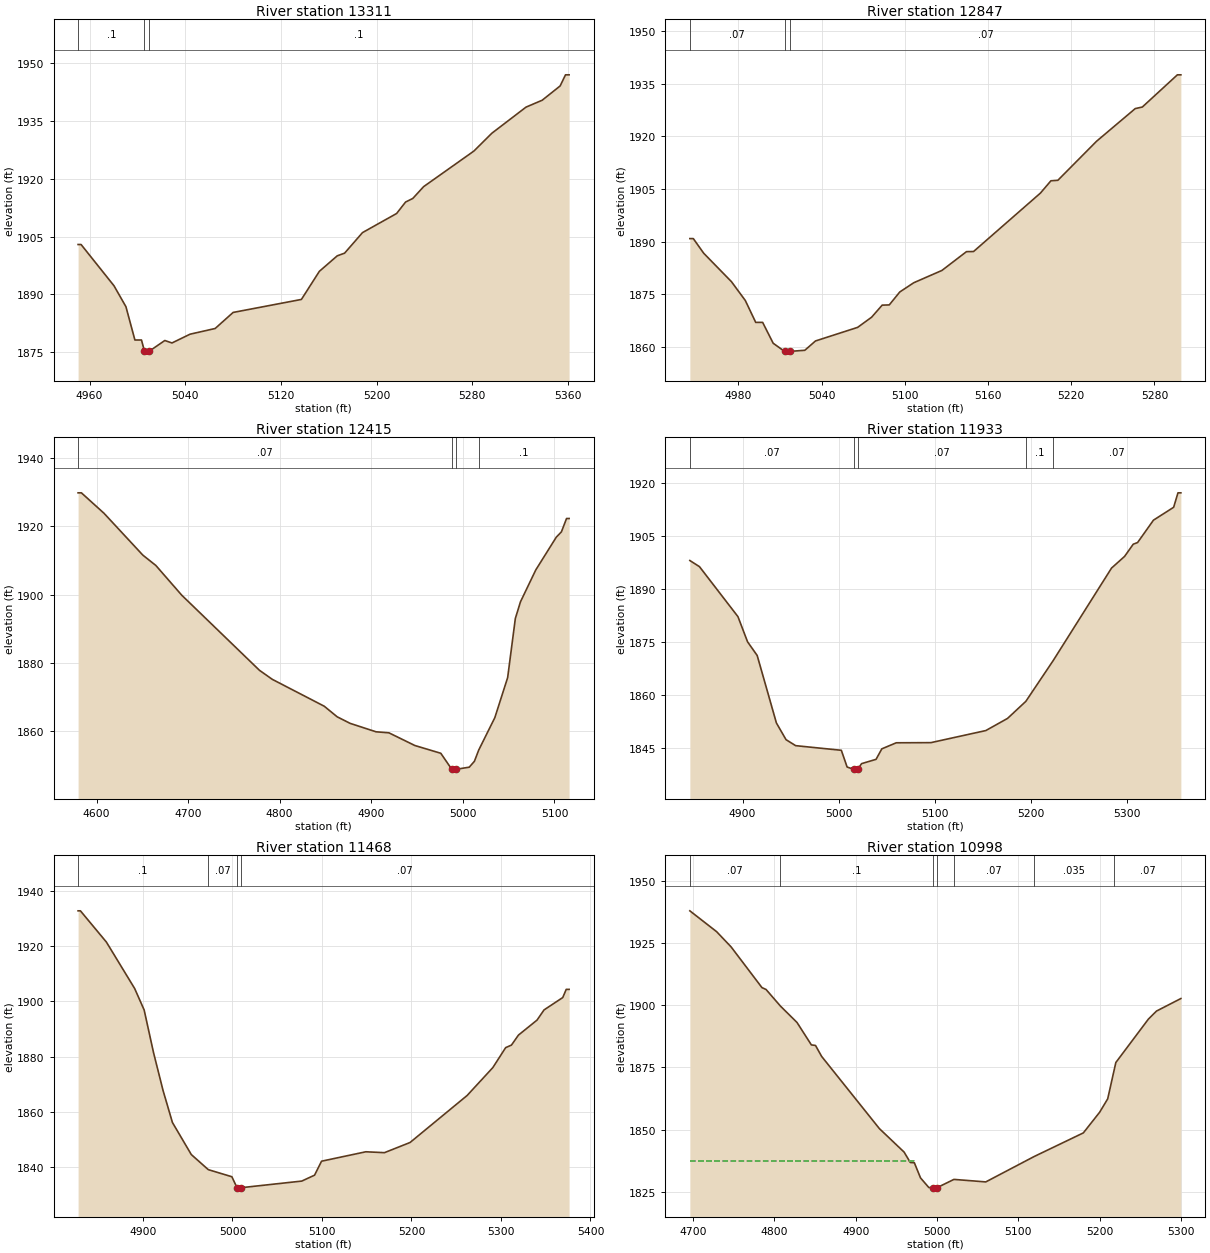
Type RM Length L Ch R = 1 ,13311   ,464,464,464
BEGIN DESCRIPTION:
Stream0002 29.0
END DESCRIPTION:
XS GIS Cut Line= 3
      1960774.99       13943025.        1960725.       13943025.
      1960425.04     13942825.02
#Sta/Elev= 30
  4950.4 1902.93  4952.9 1902.93  4980.4 1892.22  4990.4 1886.77  4997.9 1878.12
  5003.4 1878.12  5005.9 1875.21  5006.2 1874.71  5009.9 1875.21  5022.9 1877.99
  5028.9 1877.35    5044 1879.63    5065 1881.11    5080 1885.28  5137.1 1888.66
  5152.1 1895.96  5167.1    1900  5173.2 1900.68  5188.2 1906.03  5216.7 1910.99
  5224.2 1913.97  5230.2 1914.89  5239.3 1917.97  5281.3 1927.21  5296.3 1931.84
  5324.9 1938.63  5338.4 1940.42  5353.4 1944.13  5357.9 1947.02  5360.9 1947.02
#Mann= 3 ,-1 , 0
  4950.4      .1       0  5005.9     .05       0  5009.9      .1       0
Bank Sta=5005.9,5009.9
XS Rating Curve= 0 ,0
Exp/Cntr=0.3,0.1

Type RM Length L Ch R = 1 ,12847   ,432,432,432
BEGIN DESCRIPTION:
Stream0002 28.0
END DESCRIPTION:
XS GIS Cut Line= 3
        1960825.       13942575.        1960775.       13942575.
      1960475.04     13942624.99
#Sta/Elev= 30
    4945 1890.91  4947.5 1890.91    4955 1886.74    4975 1878.65    4985 1873.29
  4992.5 1867.06  4997.5 1867.06  5005.1 1861.12  5013.3 1858.81  5013.5 1858.31
  5017.3 1858.81  5027.9 1859.12  5035.6 1861.77    5066 1865.64  5076.1 1868.54
  5083.7 1871.97  5088.8 1872.03  5096.4 1875.72  5106.5 1878.35  5126.8 1881.85
  5144.5  1887.2  5149.6 1887.23  5197.8 1903.86  5205.4 1907.37  5210.4 1907.51
  5238.3 1918.62  5266.2 1927.92  5271.3 1928.36  5296.6 1937.53  5299.1 1937.53
#Mann= 3 ,-1 , 0
    4945     .07       0  5013.3     .05       0  5017.3     .07       0
Bank Sta=5013.3,5017.3
XS Rating Curve= 0 ,0
Exp/Cntr=0.3,0.1

Type RM Length L Ch R = 1 ,12415   ,482,482,482
BEGIN DESCRIPTION:
Stream0002 27.0
END DESCRIPTION:
XS GIS Cut Line= 3
      1961075.01     13942475.01        1960775.       13942175.
      1960724.99     13942074.99
#Sta/Elev= 30
  4579.9 1929.74  4583.5 1929.74  4608.2 1923.76  4650.6 1911.52  4664.8  1908.5
  4693.1  1899.8  4777.9 1877.85    4792 1875.19  4848.6 1867.35  4862.8 1864.24
  4876.9 1862.33  4905.2 1859.86  4919.3 1859.56  4947.6 1855.85  4975.9 1853.58
    4988 1848.86  4988.3 1848.36    4992 1848.86    5007 1849.52  5012.6 1851.23
  5017.3 1854.51  5034.9 1863.99  5048.9  1875.7  5057.3 1892.99  5062.9 1897.87
  5079.6 1907.18    5102 1916.77  5107.6 1918.32  5113.2 1922.23    5116 1922.23
#Mann= 4 ,-1 , 0
  4579.9     .07       0    4988     .05       0    4992     .07       0
  5017.3      .1       0
Bank Sta=4988,4992
XS Rating Curve= 0 ,0
Exp/Cntr=0.3,0.1

Type RM Length L Ch R = 1 ,11933   ,465,465,465
BEGIN DESCRIPTION:
Stream0002 26.0
END DESCRIPTION:
XS GIS Cut Line= 3
        1961225.     13942224.99        1961225.       13942075.
      1960925.03     13941875.02
#Sta/Elev= 30
  4845.2 1898.03  4855.2  1896.3  4895.2 1882.19  4905.2 1875.08  4915.2 1871.23
  4935.2 1852.17  4945.2 1847.46  4955.2 1845.77  5002.7 1844.46  5008.7 1839.74
  5015.7 1839.08    5016 1838.58  5019.7 1839.08  5023.7 1840.69  5038.8 1841.91
  5044.8 1844.87  5059.8 1846.58  5095.8 1846.62  5152.9 1850.03  5175.5 1853.46
  5194.5 1858.27  5222.9 1869.76  5283.6 1895.89  5297.2  1899.2  5306.2 1902.64
  5310.7  1903.1  5327.2 1909.42  5348.2 1913.06  5352.7 1917.14  5355.7 1917.14
#Mann= 5 ,-1 , 0
  4845.2     .07       0  5015.7     .05       0  5019.7     .07       0
  5194.5      .1       0  5222.9     .07       0
Bank Sta=5015.7,5019.7
XS Rating Curve= 0 ,0
Exp/Cntr=0.3,0.1

Type RM Length L Ch R = 1 ,11468   ,470,470,470
BEGIN DESCRIPTION:
Stream0002 25.0
END DESCRIPTION:
XS GIS Cut Line= 3
        1961525.       13941725.        1961375.       13941675.
      1961075.02     13941425.02
#Sta/Elev= 30
  4827.5 1932.82  4830.1 1932.82  4859.1 1921.52  4890.7  1904.7  4901.3 1896.94
  4911.8 1881.47  4922.4 1867.81  4932.9  1856.2    4954 1844.58    4973 1839.12
  4999.3 1836.56  5005.1 1832.57  5005.3 1832.07  5009.1 1832.57  5077.4 1834.98
  5091.7 1837.12  5099.5 1842.18    5149 1845.59  5169.8 1845.27  5198.4 1848.95
  5262.2 1865.98  5290.9 1876.07  5305.2 1883.29  5311.7 1884.22  5319.5 1887.83
  5340.3 1893.27  5348.1 1896.95    5369 1901.42  5372.9 1904.39  5376.1 1904.39
#Mann= 4 ,-1 , 0
  4827.5      .1       0    4973     .07       0  5005.1     .05       0
  5009.1     .07       0
Bank Sta=5005.1,5009.1
XS Rating Curve= 0 ,0
Exp/Cntr=0.3,0.1

Type RM Length L Ch R = 1 ,10998   ,476,476,476
BEGIN DESCRIPTION:
Stream0002 24.0
END DESCRIPTION:
XS GIS Cut Line= 3
      1961674.98       13941275.        1961375.       13941225.
      1961075.02       13941225.
#Sta/Elev= 30
  4695.9 1937.94  4728.8 1929.57  4746.6 1923.46  4784.6 1907.08  4789.7 1906.31
  4807.4 1899.63  4827.7 1893.08  4845.4 1884.05  4850.5 1883.82  4858.1 1879.39
  4929.1 1850.39  4959.5 1840.96  4967.1 1836.79  4972.1 1836.67  4979.7 1830.58
  4989.9 1826.72  4995.5 1826.57  4995.7 1826.07  4999.5 1826.57  5020.8 1829.98
    5060 1828.97  5119.4 1839.16    5180 1848.67    5200 1856.94    5210 1862.37
    5218 1874.05    5220 1876.97    5260 1894.39    5270 1897.64    5300 1902.68
#Mann= 7 ,-1 , 0
  4695.9     .07       0  4807.4      .1       0  4995.5     .05       0
  4999.5      .1       0  5020.8     .07       0  5119.4    .035       0
    5218     .07       0
#XS Ineff= 2 , 0
         4972.03 1837.48
Permanent Ineff=
       F       F
Bank Sta=4995.5,4999.5
XS Rating Curve= 0 ,0
Exp/Cntr=0.3,0.1

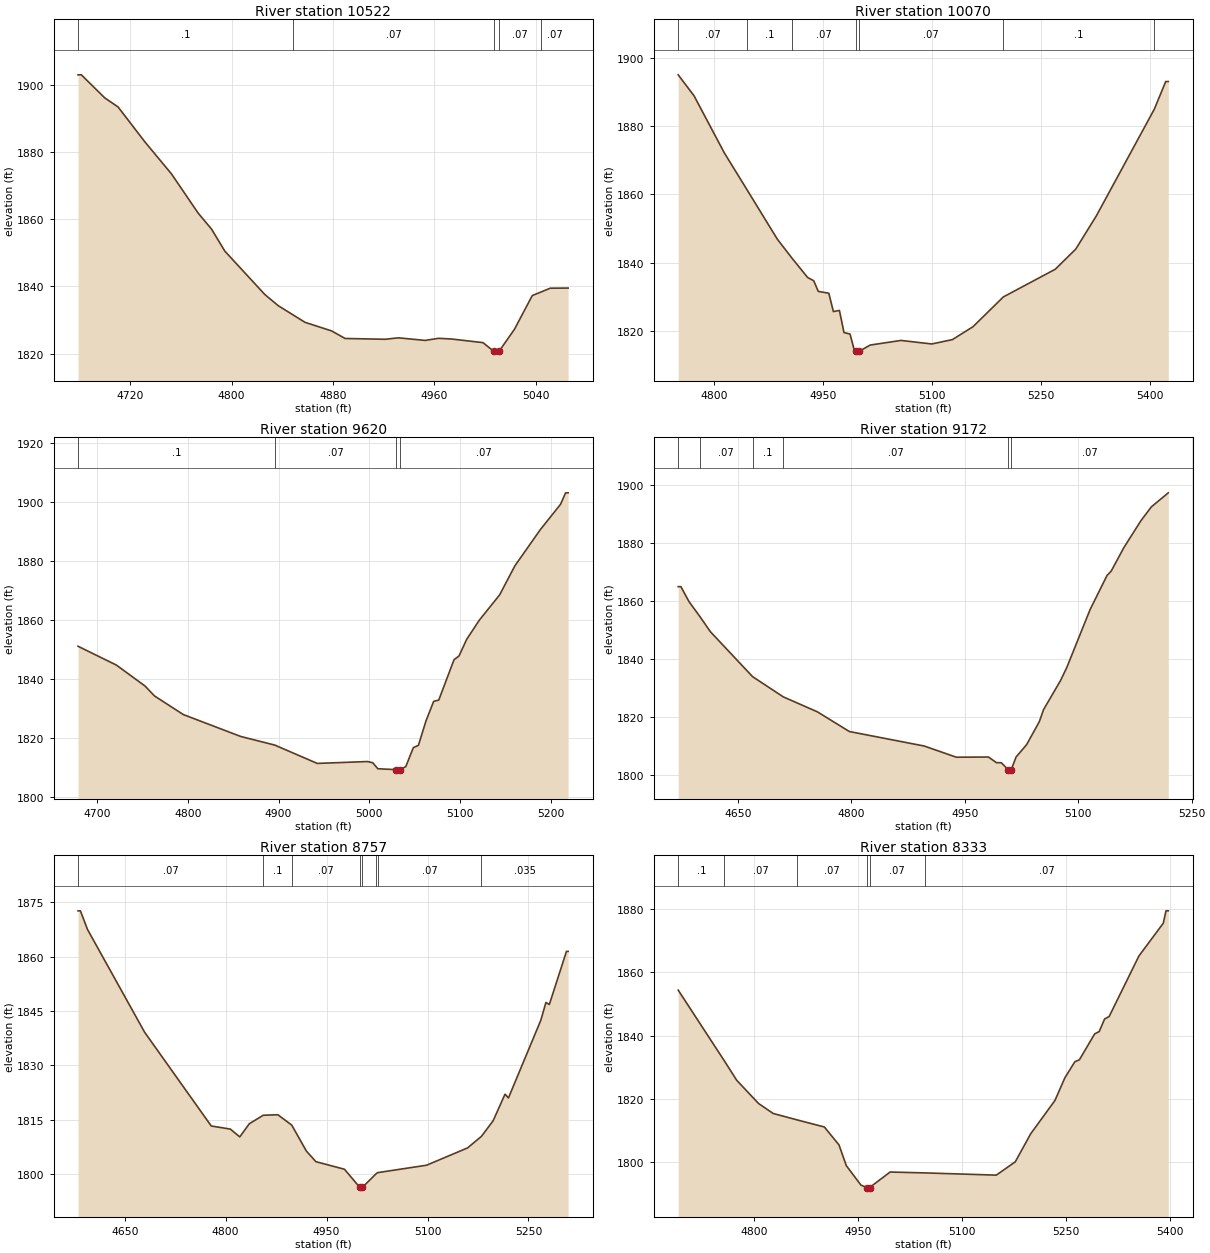
Type RM Length L Ch R = 1 ,10522   ,452,452,452
BEGIN DESCRIPTION:
Stream0002 23.0
END DESCRIPTION:
XS GIS Cut Line= 3
      1961624.97     13940924.99        1961325.       13940825.
      1961275.01     13940775.01
#Sta/Elev= 30
  4678.8 1903.11  4681.4 1903.11  4699.9 1896.23  4710.4 1893.53  4731.5 1883.15
  4752.6 1873.55  4773.6 1861.89  4784.2  1857.1  4794.7 1850.54  4826.3 1837.59
  4836.9 1834.26  4848.5 1831.54    4858 1829.31    4879 1826.75  4889.6  1824.5
  4921.2 1824.26  4931.8 1824.69  4952.8 1823.92  4963.4 1824.55  4973.9 1824.33
  4998.5 1823.26  5007.1 1820.63  5007.4 1820.13  5010.9 1820.13  5011.1 1820.63
  5023.3 1827.22  5037.4 1837.29  5044.1 1838.33  5051.6 1839.49  5065.7 1839.53
#Mann= 5 ,-1 , 0
  4678.8      .1       0  4848.5     .07       0  5007.1     .05       0
  5011.1     .07       0  5044.1     .07       0
Bank Sta=5007.1,5011.1
XS Rating Curve= 0 ,0
Exp/Cntr=0.3,0.1

Type RM Length L Ch R = 1 ,10070   ,450,450,450
BEGIN DESCRIPTION:
Stream0002 22.0
END DESCRIPTION:
XS GIS Cut Line= 3
      1961724.97     13940724.96        1961575.       13940525.
      1961275.01     13940225.01
#Sta/Elev= 30
  4750.8 1895.15  4772.6 1888.99  4814.3  1872.2  4845.4 1861.41  4887.2 1846.86
  4907.5 1841.24  4928.9  1835.6  4937.2 1834.66  4943.5 1831.52    4958 1830.98
  4964.3 1825.59  4972.6 1825.92  4978.9 1819.42  4987.2 1818.99  4993.5  1813.9
  4995.6 1813.88  4995.9 1813.38  4999.6 1813.88  5014.9 1815.75  5057.3 1817.11
  5099.7 1816.07    5128 1817.35  5156.3 1821.13  5198.1 1829.89  5269.5 1838.02
  5297.7 1843.94    5326 1853.69  5405.8 1885.06  5421.5 1893.18    5425 1893.18
#Mann= 7 ,-1 , 0
  4750.8     .07       0  4845.4      .1       0  4907.5     .07       0
  4995.6     .05       0  4999.6     .07       0  5198.1      .1       0
  5405.8     .07       0
Bank Sta=4995.6,4999.6
XS Rating Curve= 0 ,0
Exp/Cntr=0.3,0.1

Type RM Length L Ch R = 1 ,9620    ,448,448,448
BEGIN DESCRIPTION:
Stream0002 21.0
END DESCRIPTION:
XS GIS Cut Line= 3
        1961825.       13940225.        1961525.       13940125.
      1961325.03     13940025.02
#Sta/Elev= 30
  4679.2 1851.08  4721.4 1844.69    4753 1837.56  4763.5 1834.17  4795.2 1827.86
  4858.4 1820.42  4895.9 1817.49  4942.7 1811.26  4998.2  1811.9  5003.8 1811.49
  5009.4 1809.45  5029.8 1809.14    5030 1808.64  5033.8 1809.14  5040.2 1810.18
  5048.5 1816.62  5054.1 1817.42  5062.5 1825.75  5070.9 1832.36  5076.5 1832.78
  5093.3  1846.5  5098.8 1847.78  5107.2  1853.4  5121.2 1859.96  5143.6 1868.56
  5160.3 1878.39  5188.3 1890.69  5210.7 1899.35  5216.2 1903.23    5219 1903.23
#Mann= 4 ,-1 , 0
  4679.2      .1       0  4895.9     .07       0  5029.8     .05       0
  5033.8     .07       0
Bank Sta=5029.8,5033.8
XS Rating Curve= 0 ,0
Exp/Cntr=0.3,0.1

Type RM Length L Ch R = 1 ,9172    ,415,415,415
BEGIN DESCRIPTION:
Stream0002 20.0
END DESCRIPTION:
XS GIS Cut Line= 3
      1961975.03     13940025.03        1961675.       13939725.
      1961475.01       13939625.
#Sta/Elev= 30
  4571.1 1865.03  4574.7 1865.03  4585.3  1859.9  4599.8  1854.7  4613.6 1849.49
  4669.4 1833.95    4710 1826.96    4755  1821.8  4797.4 1814.98  4896.4 1809.97
  4938.8 1806.11  4981.3 1806.17  4991.9 1804.21  4998.2 1804.21  5007.4  1801.8
  5007.6  1801.3  5011.4  1801.8  5017.8 1806.19  5031.7 1810.44  5048.5 1818.38
  5054.1 1822.54  5076.5 1832.57  5084.8 1837.08  5115.6 1857.09    5138 1868.89
  5143.5 1870.39  5160.3 1878.53  5182.7 1887.77  5196.6  1892.6    5219 1897.45
#Mann= 6 ,-1 , 0
  4571.1      .1       0  4599.8     .07       0  4669.4      .1       0
    4710     .07       0  5007.4     .05       0  5011.4     .07       0
Bank Sta=5007.4,5011.4
XS Rating Curve= 0 ,0
Exp/Cntr=0.3,0.1

Type RM Length L Ch R = 1 ,8757    ,424,424,424
BEGIN DESCRIPTION:
Stream0002 19.0
END DESCRIPTION:
XS GIS Cut Line= 3
      1962224.99     13939724.99        1961925.       13939425.
      1961624.99       13939475.
#Sta/Elev= 30
  4580.6 1872.65  4584.1 1872.65  4594.7  1867.5  4679.6 1839.16  4778.6 1813.32
  4806.9 1812.47    4821 1810.32  4835.1 1813.93  4855.8 1816.28  4877.6 1816.42
  4898.2 1813.57    4920  1806.4  4934.1 1803.48  4976.6 1801.39  4999.3 1796.41
  4999.6 1795.91  5003.3 1796.41  5023.8 1800.18    5026 1800.46  5098.6  1802.5
  5159.5 1807.27  5180.2 1810.47  5197.5 1814.75  5215.2 1822.09  5220.3 1821.05
  5268.4 1842.47    5276 1847.38  5281.1 1846.83  5306.5 1861.46    5309 1861.46
#Mann= 8 ,-1 , 0
  4580.6     .07       0  4855.8      .1       0  4898.2     .07       0
  4999.3     .05       0  5003.3     .07       0  5023.8    .035       0
    5026     .07       0  5180.2    .035       0
Bank Sta=4999.3,5003.3
XS Rating Curve= 0 ,0
Exp/Cntr=0.3,0.1

Type RM Length L Ch R = 1 ,8333    ,476,476,476
BEGIN DESCRIPTION:
Stream0002 18.0
END DESCRIPTION:
XS GIS Cut Line= 3
      1962174.95     13939075.02        1961875.       13939175.
      1961574.99     13939425.01
#Sta/Elev= 30
  4690.4 1854.41  4756.9 1832.09  4774.7 1825.96  4806.3  1818.6  4827.4 1815.45
    4862 1813.42  4901.2 1811.18  4922.3 1805.52  4932.8 1798.99  4953.9 1792.84
  4962.4 1792.06  4962.7 1791.56  4966.4 1792.06    4996 1796.96  5046.3 1796.68
  5149.1 1795.98  5176.5 1800.19  5198.6    1809  5233.7 1819.57    5248 1826.72
  5262.4  1831.8  5268.9 1832.39    5291  1840.6  5297.5 1841.33  5305.3  1845.3
  5311.8 1846.06  5354.8  1865.2  5389.9 1875.54  5393.8 1879.45  5397.1 1879.45
#Mann= 6 ,-1 , 0
  4690.4      .1       0  4756.9     .07       0    4862     .07       0
  4962.4     .05       0  4966.4     .07       0  5046.3     .07       0
Bank Sta=4962.4,4966.4
XS Rating Curve= 0 ,0
Exp/Cntr=0.3,0.1

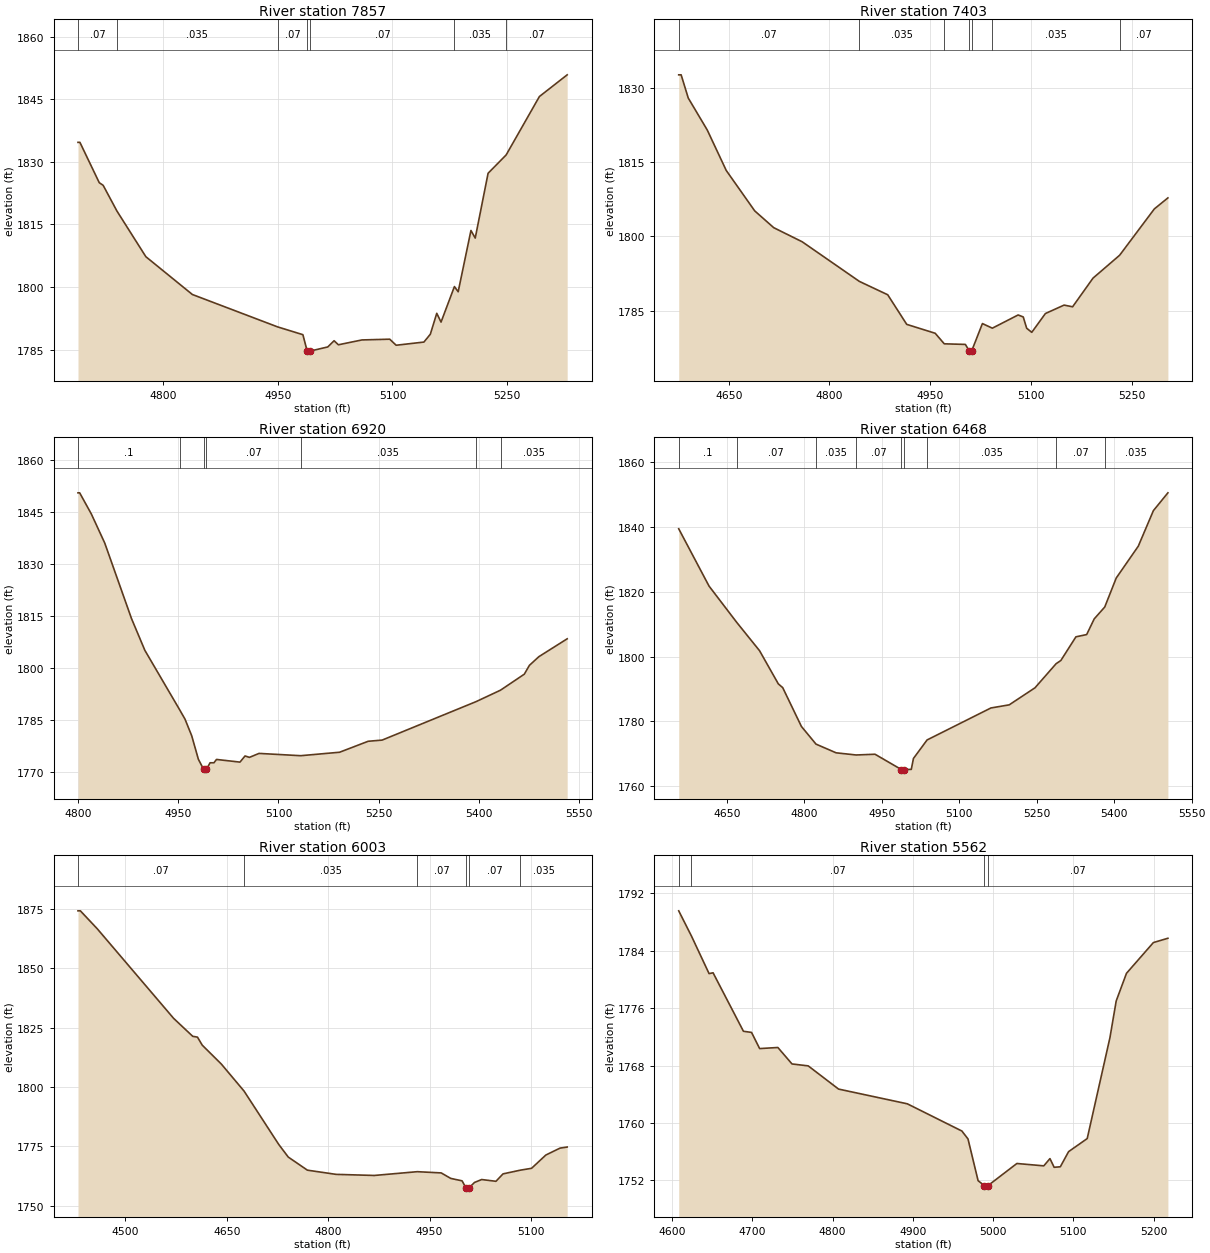
Type RM Length L Ch R = 1 ,7857    ,454,454,454
BEGIN DESCRIPTION:
Stream0002 17.0
END DESCRIPTION:
XS GIS Cut Line= 3
      1962074.97     13938725.01        1961775.       13938775.
      1961475.01     13938924.99
#Sta/Elev= 30
  4688.9 1834.65  4691.4 1834.65  4716.7 1824.98  4721.8 1824.35  4739.8 1818.19
  4777.6 1807.25  4838.4 1798.19  4949.8 1790.43  4982.9 1788.56  4988.5 1784.64
  4988.7 1784.14  4992.5 1784.64  5015.4 1785.62  5023.7 1787.11  5029.3 1786.14
  5060.1  1787.3  5096.4 1787.48  5104.8 1786.03  5141.1 1786.79  5149.5 1788.67
  5157.9 1793.68  5163.5 1791.58    5181 1800.09  5185.9 1798.84  5202.6 1813.53
  5208.2 1811.71    5225 1827.24  5248.6 1831.63  5292.1 1845.63  5328.4 1850.83
#Mann= 7 ,-1 , 0
  4688.9     .07       0  4739.8    .035       0  4949.8     .07       0
  4988.5     .05       0  4992.5     .07       0    5181    .035       0
  5248.6     .07       0
Bank Sta=4988.5,4992.5
XS Rating Curve= 0 ,0
Exp/Cntr=0.3,0.1

Type RM Length L Ch R = 1 ,7403    ,483,483,483
BEGIN DESCRIPTION:
Stream0002 16.0
END DESCRIPTION:
XS GIS Cut Line= 3
      1962075.03     13938625.03        1961775.       13938325.
      1961475.05     13938275.01
#Sta/Elev= 30
  4575.6 1832.63  4579.2 1832.63  4589.8 1827.94  4618.1 1821.48  4646.4  1813.3
  4688.8 1805.14  4717.1 1801.75  4759.5  1798.9  4844.6  1790.9  4886.8  1788.2
  4915.1 1782.22  4957.5 1780.42    4971 1778.29  5002.4 1778.17    5008 1776.91
  5008.3 1776.41    5012 1776.91  5027.8 1782.38  5042.6 1781.45    5081 1784.12
  5088.6 1783.72  5093.7 1781.44  5101.3 1780.61  5121.6 1784.41  5149.4 1786.11
  5162.1 1785.77  5192.5 1791.56  5232.1 1796.18  5283.8 1805.54    5304 1807.77
#Mann= 7 ,-1 , 0
  4575.6     .07       0  4844.6    .035       0    4971     .07       0
    5008     .05       0    5012     .07       0  5042.6    .035       0
  5232.1     .07       0
Bank Sta=5008,5012
XS Rating Curve= 0 ,0
Exp/Cntr=0.3,0.1

Type RM Length L Ch R = 1 ,6920    ,452,452,452
BEGIN DESCRIPTION:
Stream0002 15.0
END DESCRIPTION:
XS GIS Cut Line= 3
      1962074.97       13937875.        1961875.       13937875.
      1961474.98     13938225.02
#Sta/Elev= 30
  4800.2 1850.62  4802.7 1850.62  4820.2  1844.5  4840.2 1836.13  4880.2 1814.35
  4900.2 1805.18  4952.2 1788.04  4960.2 1785.34  4970.2 1780.57  4980.2 1773.77
  4988.1 1770.84  4988.4 1770.34  4992.3 1770.84  4997.7 1772.75  5003.5 1772.75
  5007.3 1773.71  5042.4 1772.94    5050 1774.71  5056.6 1774.31  5070.9 1775.45
  5133.2 1774.79  5191.4 1775.79  5234.1 1778.95    5255 1779.29  5395.5 1790.39
    5432 1793.69  5467.6 1798.31  5475.2 1800.85  5489.4 1803.36  5531.7 1808.51
#Mann= 7 ,-1 , 0
  4800.2      .1       0  4952.2     .07       0  4988.1     .05       0
  4992.3     .07       0  5133.2    .035       0  5395.5     .07       0
    5432    .035       0
Bank Sta=4988.1,4992.3
XS Rating Curve= 0 ,0
Exp/Cntr=0.3,0.1

Type RM Length L Ch R = 1 ,6468    ,465,465,465
BEGIN DESCRIPTION:
Stream0002 14.0
END DESCRIPTION:
XS GIS Cut Line= 3
      1962075.01       13937725.        1961675.       13937525.
      1961275.02     13937225.01
#Sta/Elev= 30
  4556.8 1839.34  4615.5 1821.69  4668.9 1810.56  4713.3 1801.79  4749.7 1791.56
  4758.1 1790.43  4794.4 1778.45  4822.6 1773.02  4861.5 1770.34  4900.4 1769.67
  4936.9  1769.9  4987.8  1765.2  4988.1  1764.7  4992.2  1765.2  5007.1 1765.23
  5011.3  1768.6  5037.7  1774.3  5161.3 1784.15  5196.7 1785.11  5246.7 1790.37
  5287.5 1797.78  5296.7 1798.77  5325.9 1806.06  5346.7 1806.76  5361.3 1811.58
  5381.7 1815.24    5404 1824.19  5446.7 1833.99  5475.9 1844.92    5504 1850.41
#Mann= 9 ,-1 , 0
  4556.8      .1       0  4668.9     .07       0  4822.6    .035       0
  4900.4     .07       0  4987.8     .05       0  4992.2     .07       0
  5037.7    .035       0  5287.5     .07       0  5381.7    .035       0
Bank Sta=4987.8,4992.2
XS Rating Curve= 0 ,0
Exp/Cntr=0.3,0.1

Type RM Length L Ch R = 1 ,6003    ,441,441,441
BEGIN DESCRIPTION:
Stream0002 13.0
END DESCRIPTION:
XS GIS Cut Line= 3
      1962274.99     13937524.99        1961875.       13937125.
      1961724.98     13937074.99
#Sta/Elev= 30
  4429.8 1874.21  4433.3 1874.21  4458.1 1866.71  4571.2 1828.93  4599.5 1821.35
  4606.6 1820.99  4613.6 1817.62  4641.9 1809.64  4675.5 1798.26  4726.8 1775.79
  4740.9 1770.46  4769.2 1764.94  4811.6 1763.17  4868.2 1762.71  4931.9  1764.3
  4967.2 1763.78  4981.3 1761.47  4998.1 1760.44  5003.8 1757.45  5004.1 1756.95
  5008.2 1757.45  5016.5 1759.77  5027.1 1760.99  5048.2 1760.25  5058.7 1763.38
  5084.5 1764.95  5100.9 1765.72    5122 1771.31    5143 1774.23  5153.6 1774.68
#Mann= 6 ,-1 , 0
  4429.8     .07       0  4675.5    .035       0  4931.9     .07       0
  5003.8     .05       0  5008.2     .07       0  5084.5    .035       0
Bank Sta=5003.8,5008.2
XS Rating Curve= 0 ,0
Exp/Cntr=0.3,0.1

Type RM Length L Ch R = 1 ,5562    ,479,479,479
BEGIN DESCRIPTION:
Stream0002 12.0
END DESCRIPTION:
XS GIS Cut Line= 3
      1962175.02       13936725.        1961775.       13936775.
      1961574.99       13936725.
#Sta/Elev= 30
  4608.4 1789.54  4624.3 1786.02  4646.2  1780.8  4651.2 1780.91    4689 1772.77
  4699.1 1772.61  4709.2 1770.36  4731.9 1770.51  4749.5 1768.22  4769.7 1767.95
  4807.5 1764.72  4893.1 1762.67  4961.1 1758.88  4968.7 1757.78  4981.3 1751.96
  4989.1 1751.29  4989.4 1750.79  4993.7 1751.29  5029.6 1754.36  5063.1 1754.03
  5070.8 1755.04    5076 1753.83  5083.7  1753.9    5094 1756.01  5117.2 1757.83
  5145.5 1771.88  5153.3 1776.99  5166.1 1780.84  5199.6 1785.12  5217.7 1785.72
#Mann= 4 ,-1 , 0
  4608.4      .1       0  4624.3     .07       0  4989.1     .05       0
  4993.7     .07       0
Bank Sta=4989.1,4993.7
XS Rating Curve= 0 ,0
Exp/Cntr=0.3,0.1

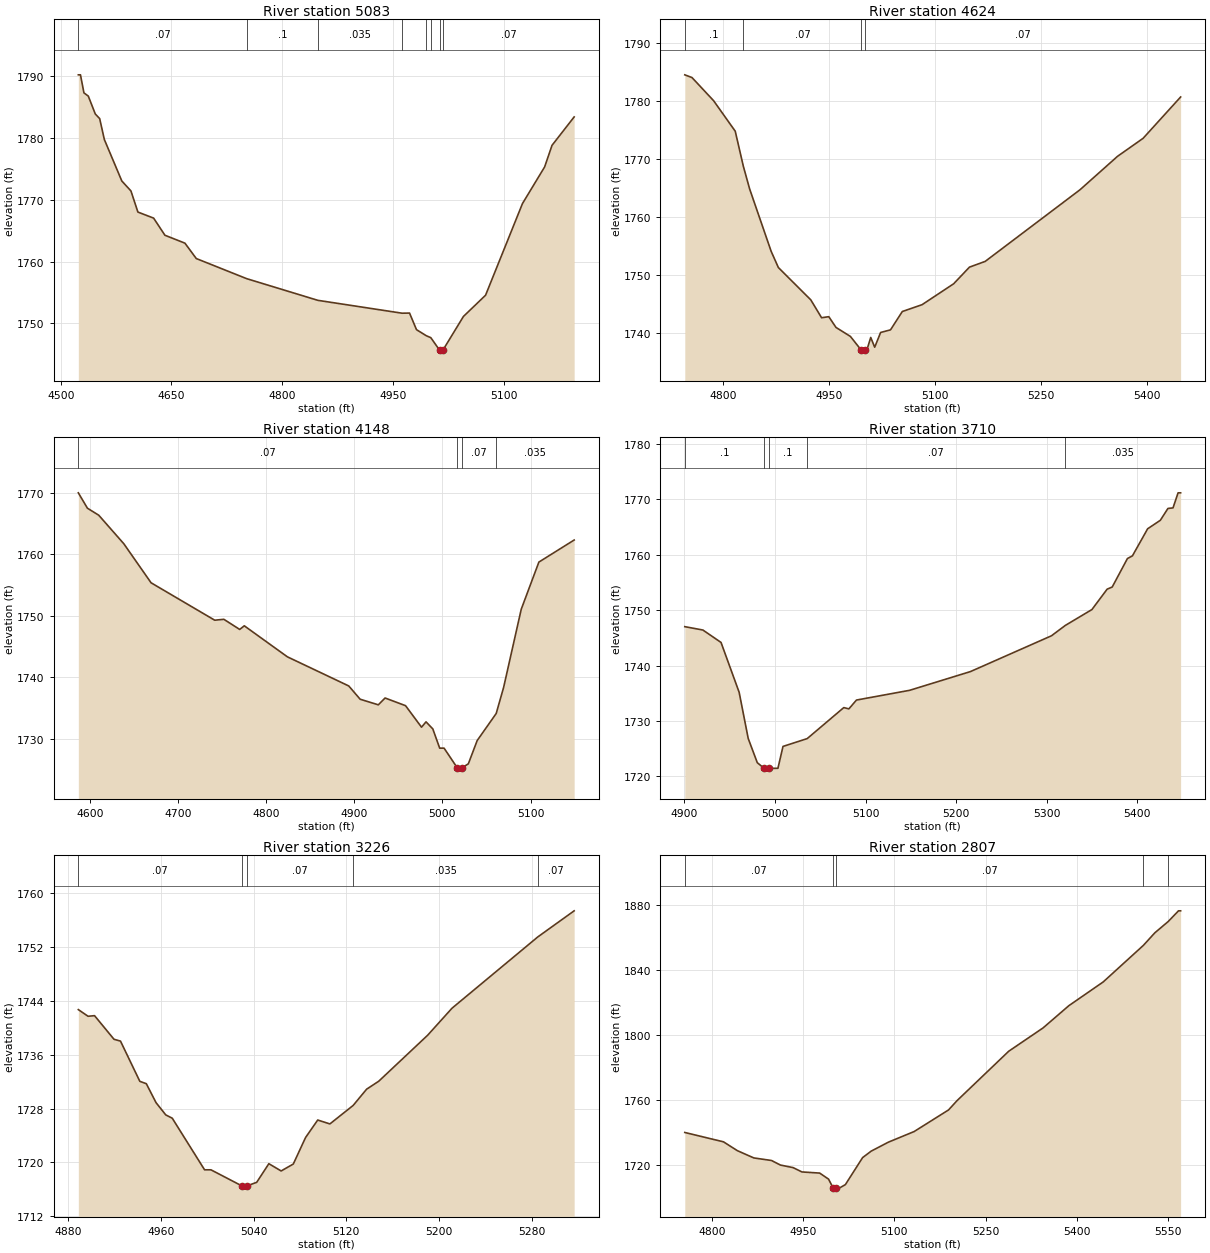
Type RM Length L Ch R = 1 ,5083    ,459,459,459
BEGIN DESCRIPTION:
Stream0002 11.0
END DESCRIPTION:
XS GIS Cut Line= 3
      1962174.98     13936624.98        1961775.       13936375.
      1961574.97       13936375.
#Sta/Elev= 30
  4523.8 1790.21  4526.7 1790.21  4531.4 1787.29  4537.3 1786.77  4546.8 1783.87
  4552.7 1783.13  4559.1 1779.73  4582.7 1773.04  4595.1 1771.42  4604.5 1768.01
  4625.8 1767.03  4641.1 1764.26  4668.2 1762.98  4683.6 1760.49    4752 1757.23
  4848.3 1753.73  4962.3 1751.65  4972.5 1751.67  4981.9 1748.99  4995.1 1748.01
  5001.3 1747.69  5013.1 1745.69  5013.5 1745.19  5017.8 1745.69  5045.5 1751.12
  5075.5 1754.56  5125.5 1769.39  5155.5 1775.31  5165.5  1778.8  5195.5  1783.4
#Mann= 8 ,-1 , 0
  4523.8     .07       0    4752      .1       0  4848.3    .035       0
  4962.3     .07       0  4995.1    .035       0  5001.3     .07       0
  5013.1     .05       0  5017.8     .07       0
Bank Sta=5013.1,5017.8
XS Rating Curve= 0 ,0
Exp/Cntr=0.3,0.1

Type RM Length L Ch R = 1 ,4624    ,476,476,476
BEGIN DESCRIPTION:
Stream0002 10.0
END DESCRIPTION:
XS GIS Cut Line= 3
      1962174.97     13935925.01        1961925.       13935975.
      1961525.03     13936174.99
#Sta/Elev= 30
  4745.6  1784.5  4755.8 1784.03  4786.4 1780.04    4817 1774.79  4828.5 1768.75
  4837.4 1764.84  4867.9 1754.08  4878.1 1751.29    4924 1745.72  4939.3 1742.64
  4949.5 1742.82  4959.7 1740.97  4980.1 1739.42  4995.6 1737.04  4995.9 1736.54
  5000.4 1737.04  5003.3 1737.04  5008.9 1739.24  5014.5 1737.56  5022.9  1740.1
  5036.9 1740.55  5053.6 1743.71  5081.6 1744.89  5126.3 1748.49  5148.7 1751.36
    5171 1752.35  5305.2 1764.69  5358.3 1770.45  5394.6 1773.56  5447.7 1780.68
#Mann= 4 ,-1 , 0
  4745.6      .1       0  4828.5     .07       0  4995.6     .05       0
  5000.4     .07       0
Bank Sta=4995.6,5000.4
XS Rating Curve= 0 ,0
Exp/Cntr=0.3,0.1

Type RM Length L Ch R = 1 ,4148    ,438,438,438
BEGIN DESCRIPTION:
Stream0002 9.0
END DESCRIPTION:
XS GIS Cut Line= 3
      1962125.04     13935675.01        1961725.       13935575.
      1961575.05       13935575.
#Sta/Elev= 30
  4587.1    1770  4597.4  1767.5  4610.3 1766.35  4638.7 1761.71  4669.6 1755.36
  4741.8 1749.27  4752.1 1749.42  4770.1 1747.77  4775.3 1748.36  4824.2 1743.31
  4893.8 1738.57  4906.7 1736.41  4927.3  1735.5    4935 1736.61  4958.2 1735.36
  4976.3 1731.86  4981.4 1732.73  4989.1 1731.58  4996.9 1728.45  5001.9 1728.45
    5017 1725.21  5017.4 1724.71  5021.8 1725.21  5029.4  1725.9  5039.4 1729.68
    5061 1734.09  5069.4 1738.33  5089.4 1751.06  5109.4 1758.73  5149.4 1762.32
#Mann= 4 ,-1 , 0
  4587.1     .07       0    5017     .05       0  5021.8     .07       0
    5061    .035       0
Bank Sta=5017,5021.8
XS Rating Curve= 0 ,0
Exp/Cntr=0.3,0.1

Type RM Length L Ch R = 1 ,3710    ,484,484,484
BEGIN DESCRIPTION:
Stream0002 8.0
END DESCRIPTION:
XS GIS Cut Line= 3
      1961975.04       13935225.        1961875.       13935225.
      1961474.96     13935425.02
#Sta/Elev= 30
  4900.4 1747.02  4920.4 1746.41  4940.4 1744.17  4960.4 1735.17  4970.4 1726.84
  4980.4 1722.47    4988 1721.44  4988.3 1720.94  4992.9 1721.44  5003.2 1721.45
  5008.8  1725.4  5035.5 1726.81  5075.9 1732.41  5081.5 1732.18  5089.9 1733.77
  5148.6 1735.53  5215.7 1738.91  5305.1 1745.37  5320.5 1747.25  5349.8 1750.11
  5366.6 1753.79  5372.2 1754.18    5389 1759.32  5394.5  1759.8  5411.3 1764.69
  5425.3 1766.22  5433.7 1768.36  5439.3 1768.46  5444.9 1771.18  5447.7 1771.18
#Mann= 5 ,-1 , 0
  4900.4      .1       0    4988     .05       0  4992.9      .1       0
  5035.5     .07       0  5320.5    .035       0
Bank Sta=4988,4992.9
XS Rating Curve= 0 ,0
Exp/Cntr=0.3,0.1

Type RM Length L Ch R = 1 ,3226    ,419,419,419
BEGIN DESCRIPTION:
Stream0002 7.0
END DESCRIPTION:
XS GIS Cut Line= 3
      1961875.02     13934724.99        1961775.       13934775.
      1961474.96     13934875.01
#Sta/Elev= 30
  4888.6 1742.72    4897 1741.73  4902.6 1741.82  4919.4 1738.31    4925 1738.04
  4941.7 1732.06  4947.3 1731.71  4955.7 1728.89  4964.1 1727.07  4969.7 1726.58
  4997.6 1718.91  5003.1 1718.91  5029.6 1716.54  5029.9 1716.04  5034.1 1716.04
  5034.5 1716.54  5042.6 1717.05  5053.1 1719.82  5063.7 1718.74  5074.2 1719.77
  5084.8 1723.71  5095.3 1726.31  5105.8 1725.73  5125.9 1728.48  5137.5 1730.89
    5148 1732.08  5190.2 1738.91  5211.2 1742.92  5285.3 1753.52  5316.7  1757.4
#Mann= 5 ,-1 , 0
  4888.6     .07       0  5029.6     .05       0  5034.5     .07       0
  5125.9    .035       0  5285.3     .07       0
Bank Sta=5029.6,5034.5
XS Rating Curve= 0 ,0
Exp/Cntr=0.3,0.1

Type RM Length L Ch R = 1 ,2807    ,464,464,464
BEGIN DESCRIPTION:
Stream0002 6.0
END DESCRIPTION:
XS GIS Cut Line= 3
      1961925.02     13934625.02        1961725.       13934475.
      1961325.01     13934075.01
#Sta/Elev= 30
  4755.2    1740  4818.8 1734.24  4841.7 1728.79  4868.8 1724.31  4897.9 1722.73
  4912.5 1719.93  4933.4 1718.34  4947.9 1715.68  4977.1 1714.98  4991.7 1711.25
  4999.5 1705.59  4999.9 1705.09  5004.7 1705.59  5008.8 1705.59  5019.4 1707.88
  5047.7  1724.5  5061.8 1728.49  5090.1 1734.02  5132.5 1740.57  5189.1 1753.88
  5203.2 1759.66  5288.1 1790.05  5344.6 1804.42  5387.1 1818.14  5443.6 1832.77
  5509.7 1855.31  5528.5 1863.03  5550.6 1870.02  5567.4 1876.57  5570.9 1876.57
#Mann= 5 ,-1 , 0
  4755.2     .07       0  4999.5     .05       0  5004.7     .07       0
  5509.7      .1       0  5550.6     .07       0
Bank Sta=4999.5,5004.7
XS Rating Curve= 0 ,0
Exp/Cntr=0.3,0.1