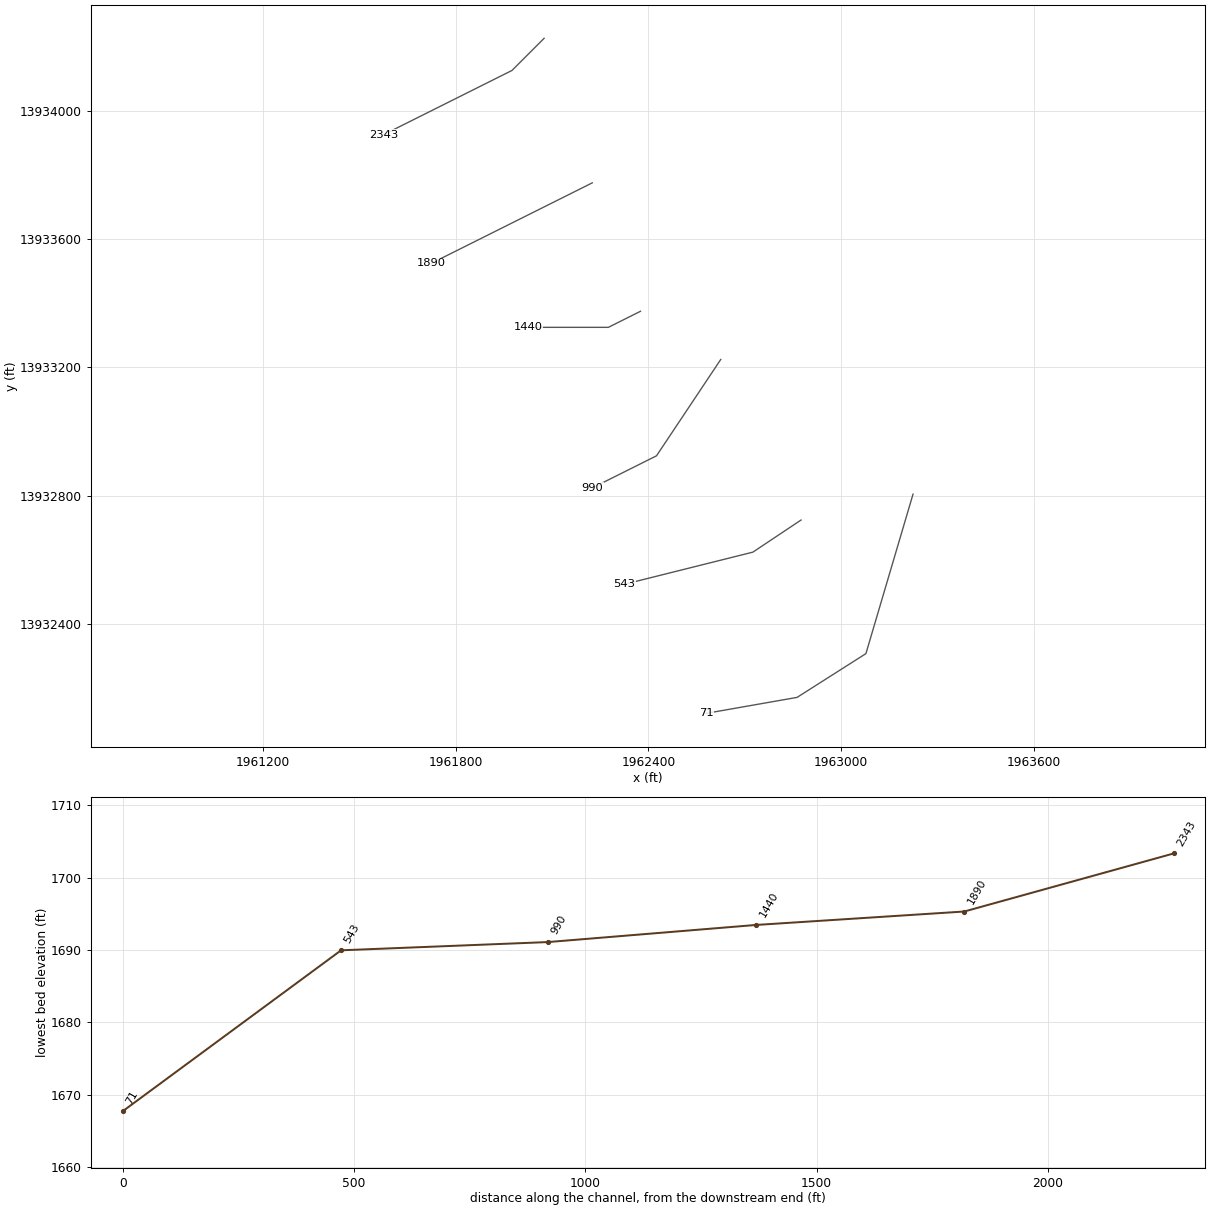
HEC-RAS study Stream0002.prj: Stream0002 Base Level Engineering

--- Stream0002.g01 (geometry) --- (continued)

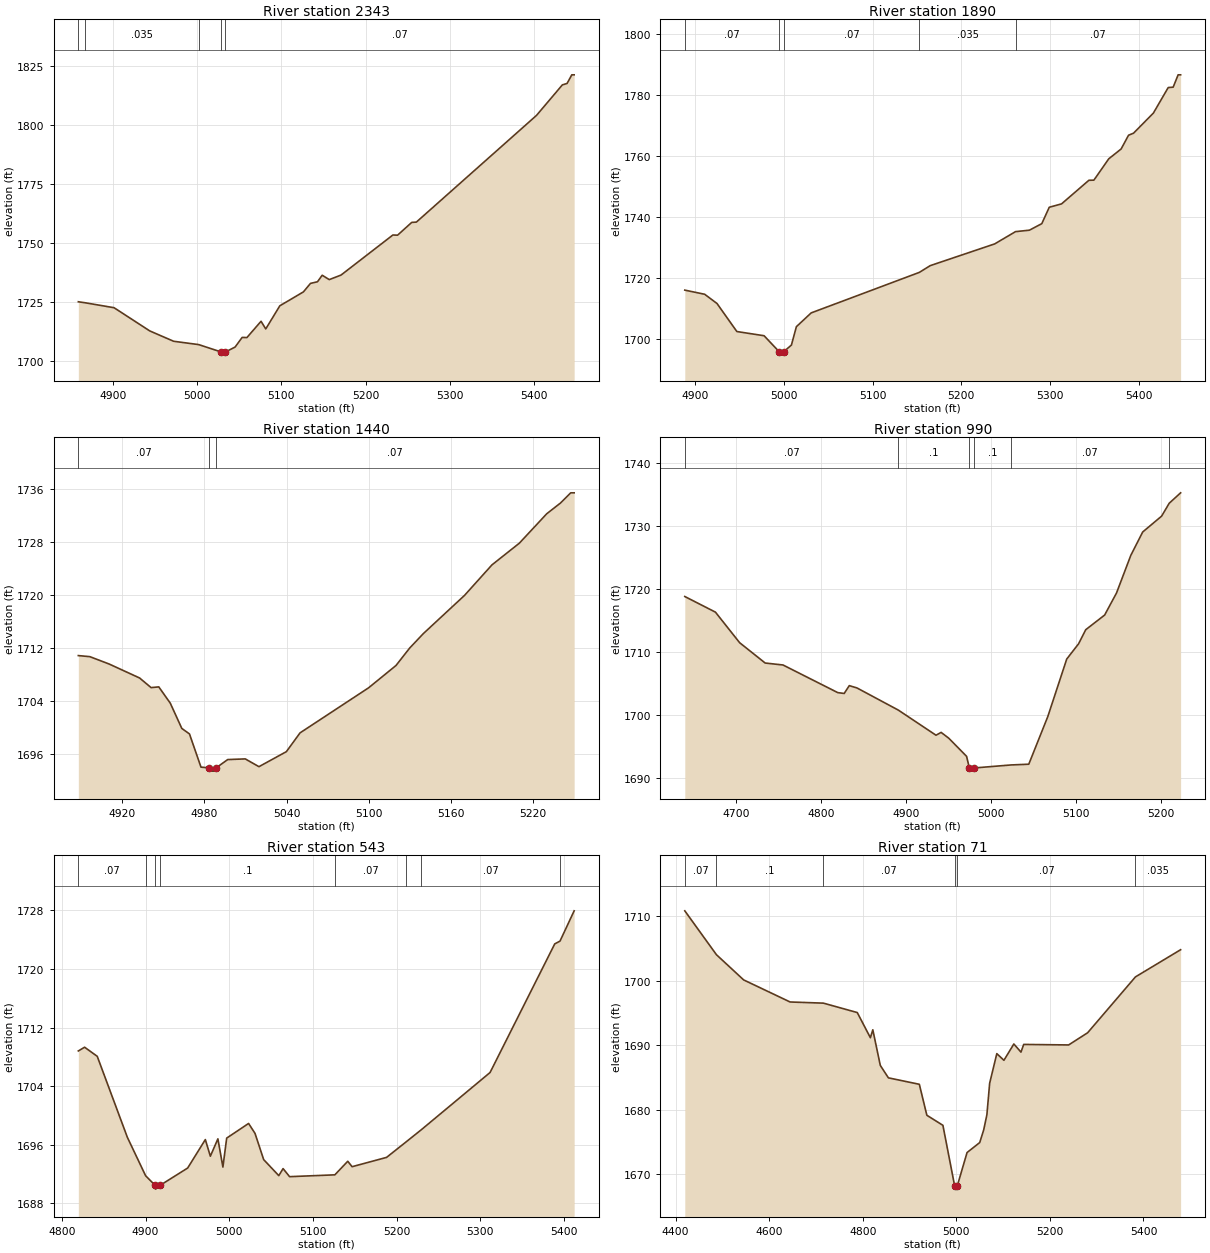
Type RM Length L Ch R = 1 ,2343    ,453,453,453
BEGIN DESCRIPTION:
Stream0002 5.0
END DESCRIPTION:
XS GIS Cut Line= 3
      1962074.98     13934224.98        1961975.       13934125.
      1961575.01     13933925.01
#Sta/Elev= 30
  4859.1 1725.13  4867.2  1724.7  4901.5 1722.61  4943.9 1712.78  4972.2  1708.4
    5002 1706.98  5028.6 1703.87    5029 1703.37  5033.8 1703.87  5045.2 1705.94
  5053.6 1710.03  5059.2 1709.96    5076 1716.86  5081.6 1713.62  5098.3 1723.42
  5126.3 1729.31  5134.7 1732.91    5143  1733.6  5148.6 1736.37    5157 1734.51
    5171 1736.45  5232.5 1753.41  5238.1 1753.34  5254.9 1758.75  5260.4 1758.88
    5403 1804.08  5433.7 1817.01  5439.3 1817.62  5444.9 1821.27  5447.7 1821.27
#Mann= 5 ,-1 , 0
  4859.1     .07       0  4867.2    .035       0    5002     .07       0
  5028.6     .05       0  5033.8     .07       0
Bank Sta=5028.6,5033.8
XS Rating Curve= 0 ,0
Exp/Cntr=0.3,0.1

Type RM Length L Ch R = 1 ,1890    ,450,450,450
BEGIN DESCRIPTION:
Stream0002 4.0
END DESCRIPTION:
XS GIS Cut Line= 3
        1962225.       13933775.        1962125.       13933725.
      1961725.01     13933525.01
#Sta/Elev= 30
  4888.2 1716.02  4910.6 1714.66  4924.5 1711.63  4946.9 1702.42  4977.6 1701.04
  4994.5 1695.83    4995 1695.33  4999.9 1695.83  5008.4 1697.98    5014 1704.01
  5030.7 1708.54  5152.6 1721.84  5164.9 1724.06  5237.6  1731.2  5261.1 1735.23
  5276.7  1735.7  5290.7 1737.85  5299.1 1743.23    5313 1744.35  5343.8 1752.09
  5349.4 1752.13  5366.2 1759.15  5380.1 1762.36  5388.5 1766.89  5394.1 1767.55
  5416.5 1774.16  5433.2 1782.54  5438.8 1782.67  5444.4 1786.72  5447.2 1786.72
#Mann= 5 ,-1 , 0
  4888.2     .07       0  4994.5     .05       0  4999.9     .07       0
  5152.6    .035       0  5261.1     .07       0
Bank Sta=4994.5,4999.9
XS Rating Curve= 0 ,0
Exp/Cntr=0.3,0.1

Type RM Length L Ch R = 1 ,1440    ,450,450,450
BEGIN DESCRIPTION:
Stream0002 3.0
END DESCRIPTION:
XS GIS Cut Line= 3
      1962375.02     13933375.01        1962275.       13933325.
      1962025.02       13933325.
#Sta/Elev= 30
  4888.1 1710.86  4896.5  1710.7  4910.5  1709.6  4932.8 1707.49  4941.2 1706.04
  4946.8 1706.15  4955.2  1703.7  4963.6  1699.9  4969.2 1699.07  4977.6 1694.07
  4983.2 1693.97  4983.6 1693.47  4988.2 1693.47  4988.7 1693.97  4997.1 1695.21
  5009.9 1695.31  5019.9 1694.14  5039.9  1696.4  5049.9 1699.23  5099.9 1706.01
  5119.9 1709.37  5129.9    1712  5139.9 1714.18  5169.9 1719.92  5189.9 1724.51
  5209.9 1727.78  5229.9 1732.21  5239.9 1733.82  5247.4 1735.36  5249.9 1735.36
#Mann= 3 ,-1 , 0
  4888.1     .07       0  4983.2     .05       0  4988.7     .07       0
Bank Sta=4983.2,4988.7
XS Rating Curve= 0 ,0
Exp/Cntr=0.3,0.1

Type RM Length L Ch R = 1 ,990     ,447,447,447
BEGIN DESCRIPTION:
Stream0002 2.0
END DESCRIPTION:
XS GIS Cut Line= 3
      1962625.01     13933225.01        1962425.       13932925.
      1962224.98     13932824.99
#Sta/Elev= 30
  4639.2 1718.82  4675.3 1716.34  4703.8 1711.49  4733.9 1708.26  4754.9 1707.95
  4819.5 1703.56    4827 1703.43    4833 1704.67    4842 1704.31  4890.9 1700.78
  4935.2  1696.8  4941.2 1697.25  4950.2 1696.33  4971.2 1693.45  4974.5  1691.6
  4974.9  1691.1    4980  1691.6  5023.6 1692.08  5044.5  1692.2  5066.9 1699.76
  5089.2 1708.89  5103.2 1711.32  5111.6 1713.55  5133.9 1715.88  5147.9 1719.39
  5164.7 1725.35  5178.7 1729.06    5201 1731.58    5210 1733.63  5223.4 1735.28
#Mann= 6 ,-1 , 0
  4639.2     .07       0  4890.9      .1       0  4974.5     .05       0
    4980      .1       0  5023.6     .07       0    5210    .035       0
Bank Sta=4974.5,4980
XS Rating Curve= 0 ,0
Exp/Cntr=0.3,0.1

Type RM Length L Ch R = 1 ,543     ,472,472,472
BEGIN DESCRIPTION:
Stream0002 1.0
END DESCRIPTION:
XS GIS Cut Line= 3
      1962875.02     13932725.01        1962725.       13932625.
      1962325.01       13932525.
#Sta/Elev= 30
  4819.7 1708.81  4827.2 1709.32  4842.3 1708.08  4878.3 1697.03  4900.1 1691.79
  4911.6 1690.46    4912 1689.96  4917.2 1690.46  4950.4 1692.84  4971.5 1696.72
  4977.5 1694.45  4986.5 1696.82  4992.5 1692.97    4997 1696.92  5023.2 1698.92
  5030.9 1697.56  5041.2 1693.99  5059.3  1691.8  5064.4 1692.76  5072.2 1691.66
  5126.3 1691.91  5141.7 1693.76  5146.9 1693.02  5188.1 1694.29  5211.4  1696.4
  5229.6 1698.06  5311.8 1705.87  5389.1 1723.42  5395.4  1723.8  5412.3 1727.93
#Mann= 8 ,-1 , 0
  4819.7     .07       0  4900.1      .1       0  4911.6     .05       0
  4917.2      .1       0  5126.3     .07       0  5211.4      .1       0
  5229.6     .07       0  5395.4    .035       0
Bank Sta=4911.6,4917.2
XS Rating Curve= 0 ,0
Exp/Cntr=0.3,0.1

Type RM Length L Ch R = 1 ,71      ,0,0,0
BEGIN DESCRIPTION:
Stream0002 0.0
END DESCRIPTION:
XS GIS Cut Line= 4
       1963223.8     13932805.63      1963077.05       13932309.
      1962862.69     13932172.73       1962579.3     13932122.95
#Sta/Elev= 30
  4419.8 1710.83  4487.4 1704.03  4545.6 1700.12  4644.8  1696.7    4716 1696.52
  4788.4 1695.06  4816.4 1691.16  4821.6 1692.39  4837.6 1686.87  4854.9 1684.94
    4921 1683.94  4937.1 1679.14  4971.4 1677.58  4996.5 1668.19    4997 1667.69
  5002.1 1668.19    5023 1673.36  5050.1 1674.91  5058.6 1676.88  5065.4 1679.23
  5071.3 1684.11  5086.6 1688.69  5101.8 1687.66    5123 1690.19  5138.2 1688.93
  5144.1 1690.12  5240.1 1690.04  5280.7 1691.93  5382.9 1700.59  5479.4  1704.8
#Mann= 6 ,-1 , 0
  4419.8     .07       0  4487.4      .1       0    4716     .07       0
  4996.5     .05       0  5002.1     .07       0  5382.9    .035       0
Bank Sta=4996.5,5002.1
XS Rating Curve= 0 ,0
Exp/Cntr=0.3,0.1

Chan Stop Cuts=-1
Use User Specified Reach Order=0
Composite Channel Slope=5