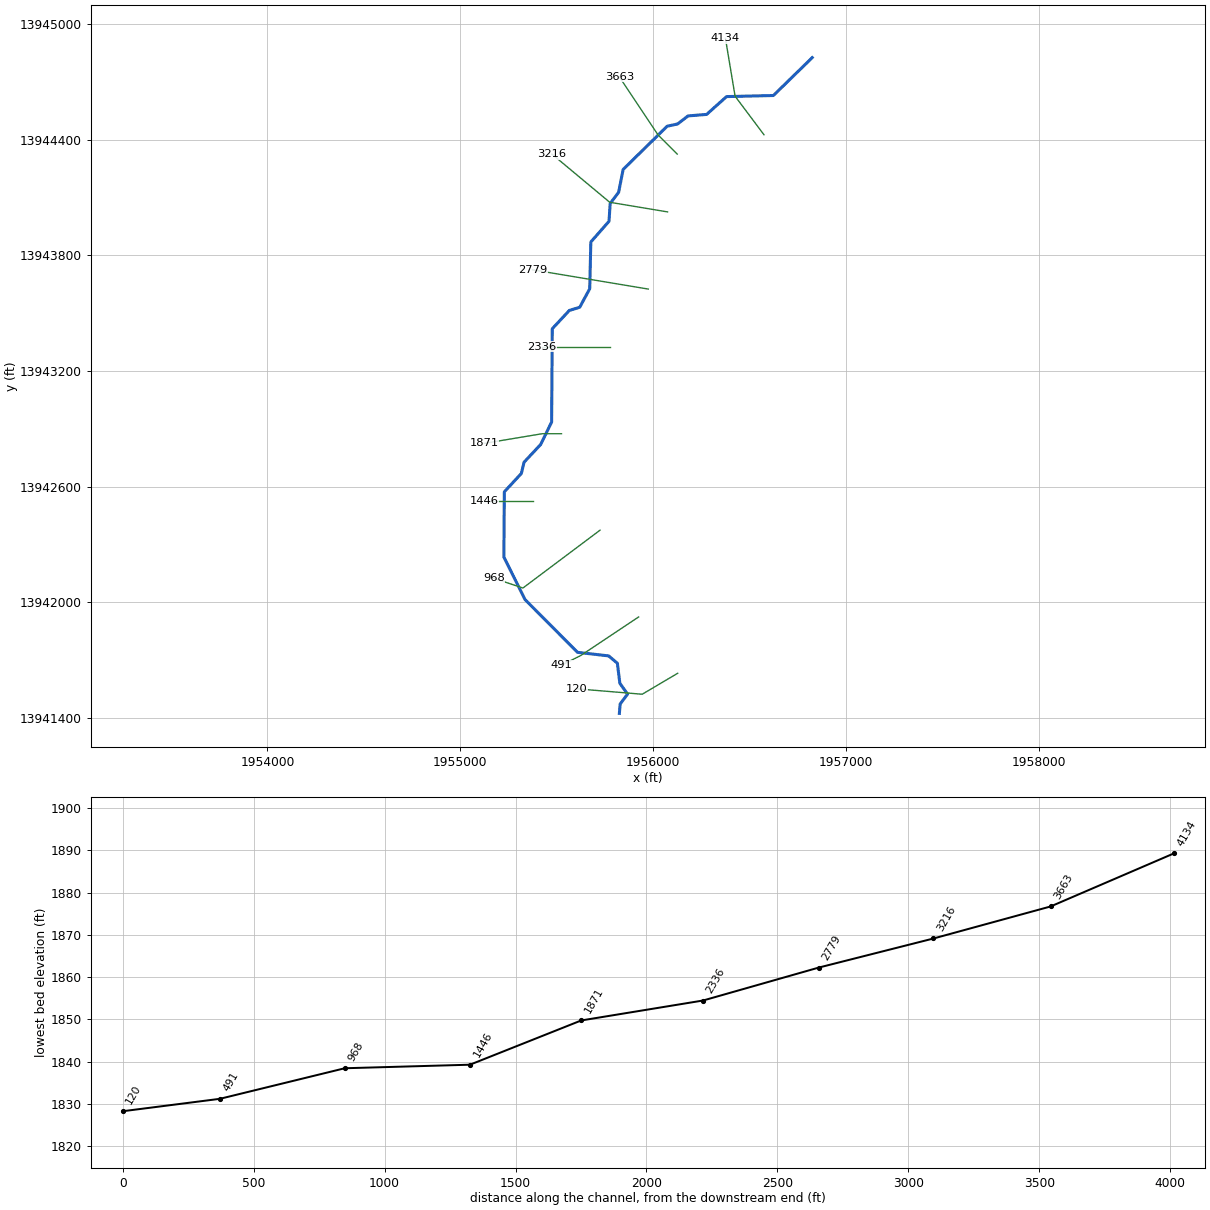
--- Stream0004.prj (project) ---

Proj Title=Stream0004 Base Level Engineering
Current Plan=p01
Default Exp/Contr=0.3,0.1
English Units
Geom File=g01
Flow File=f01
Plan File=p01
Y Axis Title=Elevation
X Axis Title(PF)=Main Channel Distance
X Axis Title(XS)=Station
BEGIN DESCRIPTION:
Stream0004
END DESCRIPTION:
DSS Export Rating Curves= 0
DSS Export Rating Curve Sorted= 0
DSS Export Volume Flow Curves= 0
DXF OffsetX= 0
DXF OffsetY= 0
DXF ScaleX= 1
DXF ScaleY= 10

--- Stream0004.p01 (plan) ---

Plan Title=Multiple Run
Short Identifier=Multiple
Geom File=g01
Flow File=f01
Subcritical Flow
K Sum by GR= 0
Std Step Tol= 0.01
Critical Tol= 0.01
Num of Std Step Trials= 20
Max Error Tol= 0.3
Flow Tol Ratio= 0.001
Split Flow NTrial= 30
Split Flow Tol= 0.02
Split Flow Ratio= 0.02
Log Output Level= 0
Friction Slope Method= 1
Unsteady Friction Slope Method= 2
Unsteady Bridges Friction Slope Method= 1
Parabolic Critical Depth
Global Vel Dist=  1 , 1 , 1
Global Log Level= 0
CheckData=True
Encroach Param= -1, 0, 0, 0
BEGIN DESCRIPTION:
Multiple Run
END DESCRIPTION:

--- Stream0004.f01 (steady flow) ---

Flow Title=Multiple
Number of Profiles=7
Profile Names=10-year,25-year,50-year,1pct_min,100-year,1pct_plu,500-year
River Rch & RM= Stream0004,Reach-1,4134
    1341    2319    3264    2222    4433    8844    8071
River Rch & RM= Stream0004,Reach-1,3663
    1578    2747    3881    2649    5286   10547    9684
Boundary for River Rch & Prof#=Stream0004,Reach-1,1
Up Type=0
Dn Type=3
Dn Slope=0.005
Boundary for River Rch & Prof#=Stream0004,Reach-1,2
Up Type=0
Dn Type=3
Dn Slope=0.005
Boundary for River Rch & Prof#=Stream0004,Reach-1,3
Up Type=0
Dn Type=3
Dn Slope=0.005
Boundary for River Rch & Prof#=Stream0004,Reach-1,4
Up Type=0
Dn Type=3
Dn Slope=0.005
Boundary for River Rch & Prof#=Stream0004,Reach-1,5
Up Type=0
Dn Type=3
Dn Slope=0.005
Boundary for River Rch & Prof#=Stream0004,Reach-1,6
Up Type=0
Dn Type=3
Dn Slope=0.005
Boundary for River Rch & Prof#=Stream0004,Reach-1,7
Up Type=0
Dn Type=3
Dn Slope=0.005

--- Stream0004.g01 (geometry) ---

Geom Title=Existing Conditions
Program Version=4.10

River Reach=Stream0004      ,Reach-1
Reach XY= 30
        1956825.       13944825.      1956623.54     13944628.54
      1956380.86     13944622.93      1956277.42     13944530.54
      1956180.97     13944522.67      1956127.17     13944481.14
       1956072.7     13944469.17      1955844.63     13944245.16
      1955821.14      13944126.6      1955777.36     13944069.02
      1955771.38      13943976.5      1955677.07     13943869.14
      1955671.26     13943626.52      1955619.41     13943530.61
      1955565.56     13943514.12      1955477.05     13943419.16
       1955473.8      13942935.5      1955416.84     13942818.95
      1955330.87     13942727.28      1955316.82     13942668.96
      1955228.55     13942573.53       1955226.2      13942235.5
      1955335.76     13942015.32      1955608.24     13941741.43
      1955769.35     13941723.02      1955814.64     13941685.16
      1955827.54      13941580.9      1955867.69     13941524.96
        1955829.     13941473.64        1955825.       13941425.

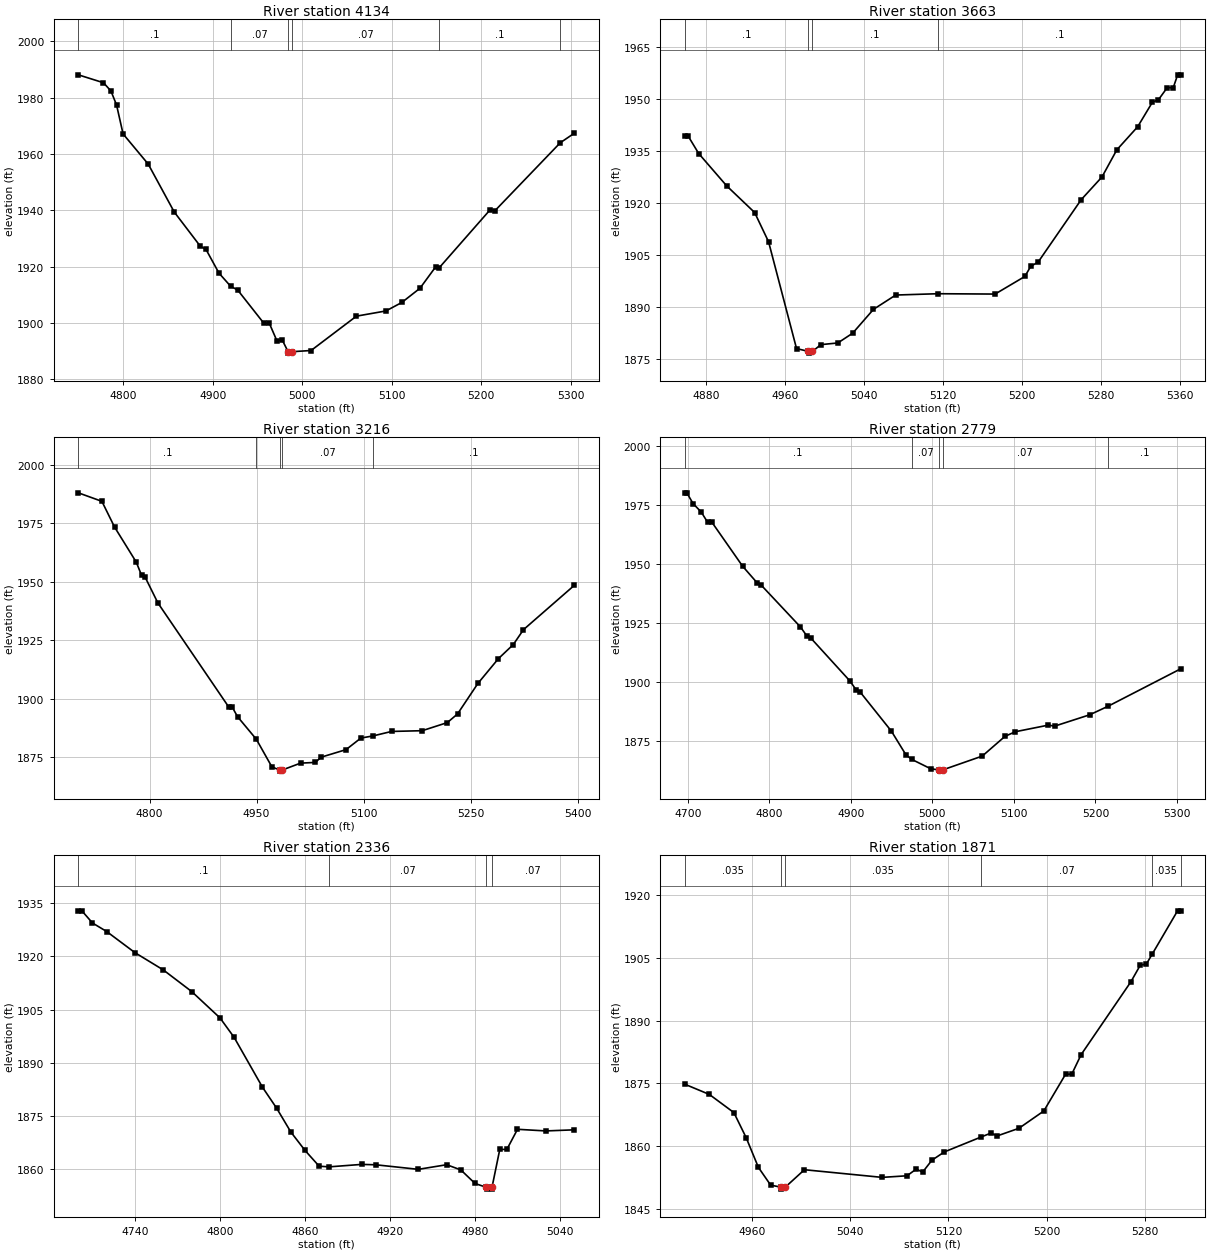
Type RM Length L Ch R = 1 ,4134    ,471,471,471
BEGIN DESCRIPTION:
Stream0004 9.0
END DESCRIPTION:
XS GIS Cut Line= 3
      1956574.97     13944425.03        1956425.       13944625.
        1956375.       13944925.
#Sta/Elev= 30
  4749.6  1988.1  4777.7 1985.29    4786 1982.38  4792.3 1977.42  4799.6 1967.12
  4827.7 1956.41  4856.8 1939.39    4886 1927.22  4892.3  1926.1  4906.8 1917.69
  4919.7 1913.08  4927.7 1911.69  4956.8 1899.95  4963.1 1899.84  4971.4 1893.76
  4977.7 1893.83    4984  1889.8  4984.3  1889.3    4988  1889.8  5009.7 1890.23
  5060.4 1902.43  5093.3 1904.27  5111.1 1907.28  5131.4 1912.33  5149.1    1920
  5152.8 1919.57  5209.9 1940.23    5215  1939.8  5288.2 1963.99  5303.7 1967.33
#Mann= 6 ,-1 , 0
  4749.6      .1       0  4919.7     .07       0    4984     .05       0
    4988     .07       0  5152.8      .1       0  5288.2     .07       0
Bank Sta=4984,4988
XS Rating Curve= 0 ,0
Exp/Cntr=0.3,0.1

Type RM Length L Ch R = 1 ,3663    ,447,447,447
BEGIN DESCRIPTION:
Stream0004 8.0
END DESCRIPTION:
XS GIS Cut Line= 3
      1956124.97     13944325.03        1956025.       13944425.
      1955825.02     13944724.97
#Sta/Elev= 30
  4858.4 1939.23  4861.9 1939.23  4872.5 1934.24  4900.8 1924.93  4929.1 1917.25
  4943.2 1908.82  4971.5 1878.04  4983.6 1877.23  4983.9 1876.73  4987.6 1877.23
  4996.2 1879.18  5013.3 1879.66  5028.3 1882.47  5049.4 1889.35  5071.9 1893.47
  5114.6 1893.85  5172.5 1893.75  5202.6 1898.82  5208.6 1901.75  5216.1 1902.98
  5259.7 1920.97  5280.7  1927.5  5295.7 1935.31  5316.8 1941.96  5331.8 1949.07
  5337.8 1949.73  5346.8 1953.27  5352.8 1953.21  5357.3 1956.93  5360.3 1956.93
#Mann= 4 ,-1 , 0
  4858.4      .1       0  4983.6     .05       0  4987.6      .1       0
  5114.6      .1       0
Bank Sta=4983.6,4987.6
XS Rating Curve= 0 ,0
Exp/Cntr=0.3,0.1

Type RM Length L Ch R = 1 ,3216    ,437,437,437
BEGIN DESCRIPTION:
Stream0004 7.0
END DESCRIPTION:
XS GIS Cut Line= 3
      1956075.02       13944025.        1955775.       13944075.
      1955474.98     13944325.02
#Sta/Elev= 30
  4700.2 1987.95  4733.2 1984.32  4750.9 1973.37  4781.3  1958.4  4788.9 1952.68
    4794 1951.82  4811.7 1940.93  4910.6 1896.67  4915.6 1896.58  4923.3 1892.38
  4949.6 1882.75  4971.4 1870.96  4982.1 1869.65  4982.3 1869.15  4986.1 1869.65
  5011.5 1872.56  5032.3 1872.87  5040.2 1875.08  5075.3 1878.33  5096.1 1883.27
  5112.8 1884.16  5139.1 1886.09    5182 1886.41  5217.2 1889.87  5231.5 1893.56
  5260.1 1906.61  5288.8 1917.18  5309.6 1923.17  5323.9 1929.54  5394.9  1948.4
#Mann= 5 ,-1 , 0
  4700.2      .1       0  4949.6     .07       0  4982.1     .05       0
  4986.1     .07       0  5112.8      .1       0
Bank Sta=4982.1,4986.1
XS Rating Curve= 0 ,0
Exp/Cntr=0.3,0.1

Type RM Length L Ch R = 1 ,2779    ,443,443,443
BEGIN DESCRIPTION:
Stream0004 6.0
END DESCRIPTION:
XS GIS Cut Line= 3
      1955974.97       13943625.        1955675.       13943675.
      1955375.05     13943724.99
#Sta/Elev= 30
  4696.3 1980.22  4698.8 1980.22  4706.4 1975.68  4716.5 1972.06  4724.2 1967.78
  4729.2 1967.93  4767.2 1949.13    4785 1942.08    4790 1941.11  4838.2 1923.37
  4845.8 1919.66  4850.9 1918.66    4899 1900.43  4906.6 1896.63  4911.7 1895.66
  4949.7 1879.23  4967.5 1869.22  4974.5 1867.29  4997.9 1863.29  5008.5 1862.78
  5008.8 1862.28  5012.5 1862.78  5061.2 1868.66  5089.1 1877.03  5101.8 1878.98
  5142.3 1881.78  5149.9 1881.34    5193 1886.16  5215.4 1889.76  5304.5 1905.62
#Mann= 5 ,-1 , 0
  4696.3      .1       0  4974.5     .07       0  5008.5     .05       0
  5012.5     .07       0  5215.4      .1       0
Bank Sta=5008.5,5012.5
XS Rating Curve= 0 ,0
Exp/Cntr=0.3,0.1

Type RM Length L Ch R = 1 ,2336    ,465,465,465
BEGIN DESCRIPTION:
Stream0004 5.0
END DESCRIPTION:
XS GIS Cut Line= 3
      1955775.01       13943325.        1955475.       13943325.
      1955425.01       13943325.
#Sta/Elev= 30
  4699.9 1932.79  4702.4 1932.79  4709.9 1929.36  4719.9 1926.97  4739.9 1921.01
  4759.9 1916.15  4779.9 1910.08  4799.9 1902.65  4809.9 1897.16  4829.9 1883.13
  4839.9 1877.23  4849.9 1870.54  4859.9 1865.36  4869.9 1860.91    4877 1860.73
  4899.9 1861.42  4909.9 1861.31  4939.9 1860.03  4959.9 1861.33  4969.9 1859.87
  4979.9 1856.06  4987.9 1854.96  4988.2 1854.46  4991.7 1854.46  4991.9 1854.96
  4997.4 1865.64  5002.4 1865.64  5009.9  1871.3  5029.9 1870.84  5049.9 1871.15
#Mann= 4 ,-1 , 0
  4699.9      .1       0    4877     .07       0  4987.9     .05       0
  4991.9     .07       0
Bank Sta=4987.9,4991.9
XS Rating Curve= 0 ,0
Exp/Cntr=0.3,0.1

Type RM Length L Ch R = 1 ,1871    ,425,425,425
BEGIN DESCRIPTION:
Stream0004 4.0
END DESCRIPTION:
XS GIS Cut Line= 3
      1955524.98       13942875.        1955425.       13942875.
      1955125.02       13942825.
#Sta/Elev= 30
  4905.1 1874.82  4925.1 1872.38  4945.1 1868.04  4955.1 1862.05  4965.1 1854.93
  4975.1 1850.69  4983.1 1850.24  4983.3 1849.74  4987.1 1850.24  5002.6 1854.38
  5065.9 1852.55  5086.2 1852.93  5093.8 1854.55  5098.9 1853.79  5106.5 1856.65
  5116.6 1858.63  5146.4 1862.18  5154.6 1863.14  5159.7 1862.46  5177.4 1864.28
  5197.7 1868.42  5215.4 1877.19  5220.5 1877.23  5228.1 1881.89  5268.7 1899.32
  5276.3 1903.27  5281.3 1903.56  5285.9 1905.85  5306.7 1916.27  5309.2 1916.27
#Mann= 6 ,-1 , 0
  4905.1    .035       0  4983.1    .035       0  4987.1    .035       0
  5146.4     .07       0  5285.9    .035       0  5309.2     .07       0
Bank Sta=4983.1,4987.1
XS Rating Curve= 0 ,0
Exp/Cntr=0.3,0.1

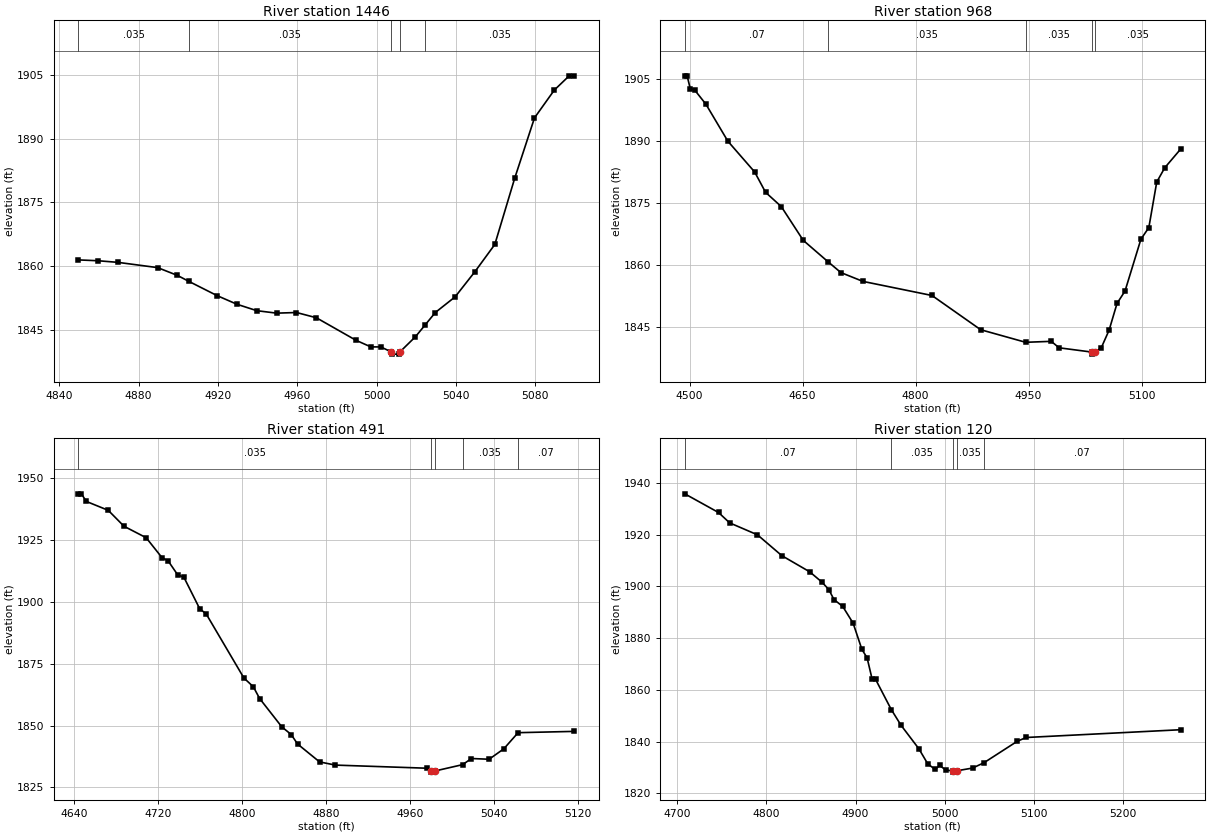
Type RM Length L Ch R = 1 ,1446    ,478,478,478
BEGIN DESCRIPTION:
Stream0004 3.0
END DESCRIPTION:
XS GIS Cut Line= 3
      1955374.96       13942525.        1955225.       13942525.
      1955124.96       13942525.
#Sta/Elev= 30
  4849.6 1861.45  4859.6 1861.25  4869.6 1860.87  4889.6 1859.63  4899.6 1857.79
  4905.3  1856.4  4919.6 1853.03  4929.6    1851  4939.6 1849.49  4949.6 1848.91
  4959.6 1849.06  4969.6 1847.83  4989.6 1842.52  4997.1 1840.96  5002.1 1840.96
  5007.5 1839.76  5007.8 1839.26  5011.4 1839.26  5011.7 1839.76  5019.6 1843.37
  5024.3 1846.04  5029.6 1849.06  5039.6 1852.76  5049.6  1858.7  5059.6 1865.09
  5069.6 1880.65  5079.6  1894.9  5089.6 1901.45  5097.1  1904.8  5099.6  1904.8
#Mann= 5 ,-1 , 0
  4849.6    .035       0  4905.3    .035       0  5007.5    .035       0
  5011.7    .035       0  5024.3    .035       0
Bank Sta=5007.5,5011.7
XS Rating Curve= 0 ,0
Exp/Cntr=0.3,0.1

Type RM Length L Ch R = 1 ,968     ,477,477,477
BEGIN DESCRIPTION:
Stream0004 2.0
END DESCRIPTION:
XS GIS Cut Line= 3
      1955724.97     13942374.97        1955325.       13942075.
      1955174.97     13942125.01
#Sta/Elev= 30
  4493.7 1905.68  4496.8 1905.68  4500.9  1902.6  4507.2 1902.16  4521.8  1898.8
  4550.9 1889.87  4586.4 1882.45  4600.9 1877.53  4621.8 1874.07  4650.9 1865.92
  4683.7 1860.76  4700.9 1858.13  4730.1    1856  4821.8 1852.59  4886.4 1844.32
  4946.1 1841.28  4980.1 1841.51  4990.5 1839.95  5033.7 1838.92    5034 1838.42
  5037.9 1838.92  5046.4 1839.92  5056.9 1844.23  5067.4 1850.68    5078 1853.67
  5099.1  1866.2  5109.6    1869  5120.1 1880.01  5130.7 1883.45  5151.8 1887.97
#Mann= 5 ,-1 , 0
  4493.7     .07       0  4683.7    .035       0  4946.1    .035       0
  5033.7    .035       0  5037.9    .035       0
Bank Sta=5033.7,5037.9
XS Rating Curve= 0 ,0
Exp/Cntr=0.3,0.1

Type RM Length L Ch R = 1 ,491     ,371,371,371
BEGIN DESCRIPTION:
Stream0004 1.0
END DESCRIPTION:
XS GIS Cut Line= 3
      1955924.98     13941924.99        1955625.       13941725.
      1955525.04     13941675.02
#Sta/Elev= 30
  4644.3 1943.62  4647.3 1943.62  4651.8 1940.57  4672.8 1936.95  4687.8 1930.52
  4708.9 1925.89  4723.9 1917.89  4729.9 1916.49  4738.9 1910.91  4744.9 1909.88
    4760 1897.12    4766 1895.16    4802 1869.22    4811 1865.66    4817 1860.92
  4838.1 1849.48  4847.1 1846.36  4853.1 1842.55  4874.1 1835.31  4889.2 1834.02
  4976.3 1832.76  4980.2 1831.68  4980.5 1831.18  4984.4 1831.68  5010.3  1834.2
  5018.8 1836.68  5035.6 1836.38  5049.6  1840.6  5063.2 1847.12  5116.6 1847.64
#Mann= 5 ,-1 , 0
  4644.3    .035       0  4980.2    .035       0  4984.4    .035       0
  5010.3    .035       0  5063.2     .07       0
Bank Sta=4980.2,4984.4
XS Rating Curve= 0 ,0
Exp/Cntr=0.3,0.1

Type RM Length L Ch R = 1 ,120     ,0,0,0
BEGIN DESCRIPTION:
Stream0004 0.0
END DESCRIPTION:
XS GIS Cut Line= 3
      1956127.57     13941633.04       1955943.4     13941524.21
      1955602.49     13941552.49
#Sta/Elev= 30
  4708.5 1935.74  4746.3 1928.53  4758.8 1924.52    4790  1919.9  4817.3 1911.86
  4848.6 1905.61  4862.5 1901.57    4870 1898.75  4875.8 1894.89  4885.6 1892.24
  4897.3 1885.74  4907.1 1875.63  4912.9 1872.42  4918.6  1864.1  4922.4  1864.1
    4940 1852.43  4950.9 1846.38    4971 1837.25    4981  1831.4  4989.3 1829.28
  4994.3 1830.84  5001.1 1829.03    5009 1828.74  5009.3 1828.24  5013.2 1828.74
  5031.2 1829.81  5043.9 1831.85  5081.4 1840.18  5091.4 1841.62  5264.5 1844.62
#Mann= 5 ,-1 , 0
  4708.5     .07       0    4940    .035       0    5009    .035       0
  5013.2    .035       0  5043.9     .07       0
Bank Sta=5009,5013.2
XS Rating Curve= 0 ,0
Exp/Cntr=0.3,0.1

Chan Stop Cuts=-1
Use User Specified Reach Order=0
Composite Channel Slope=5