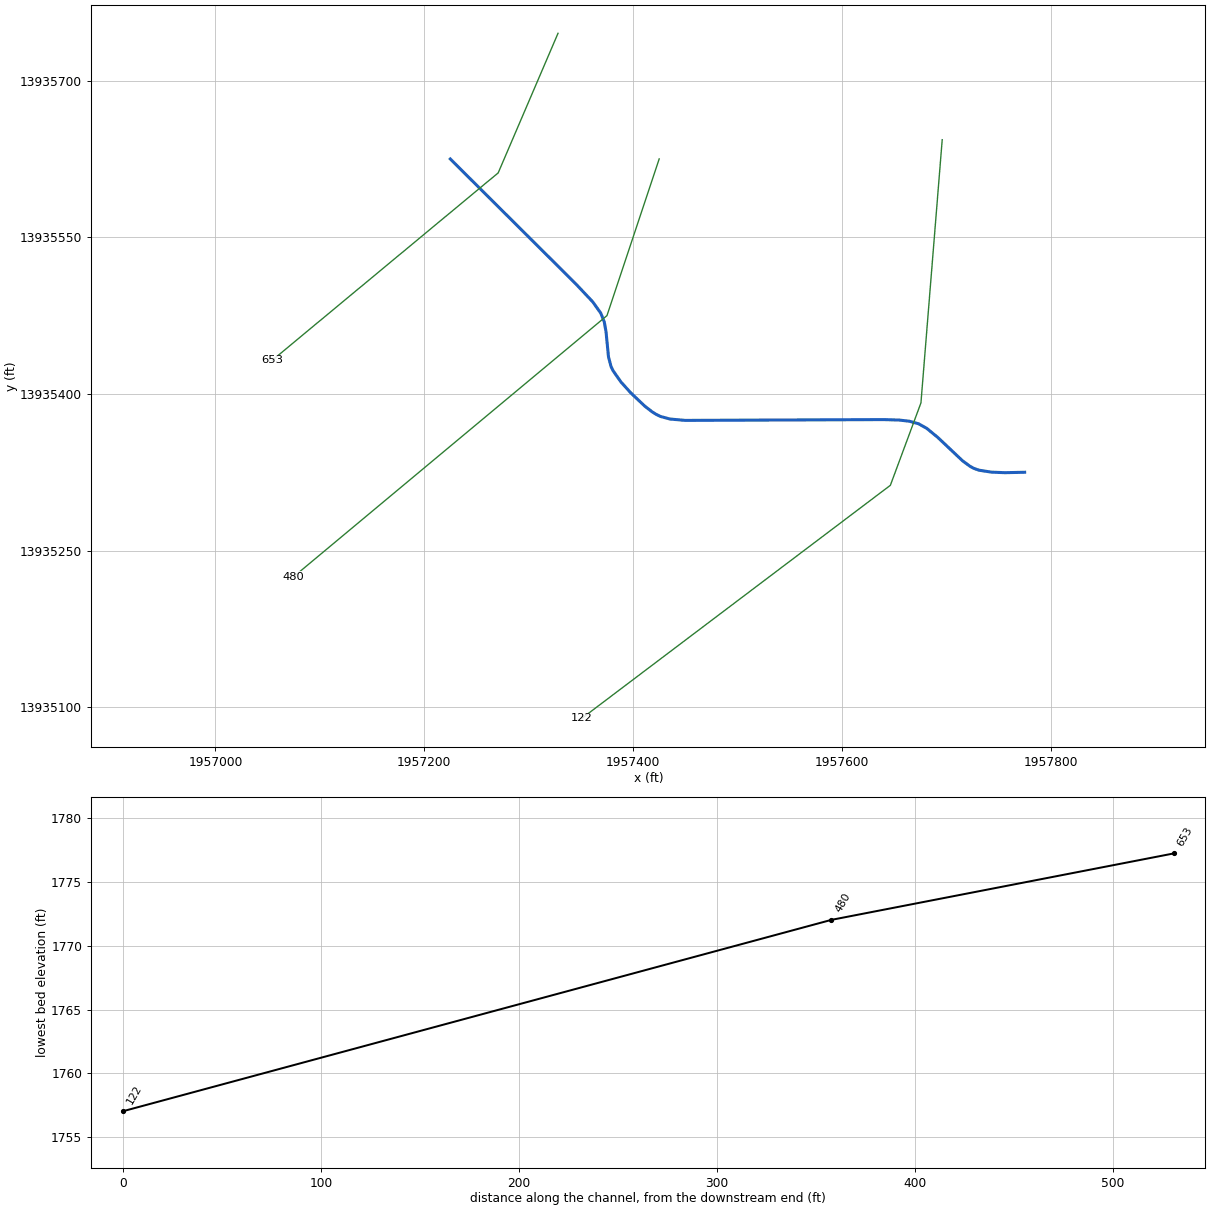
--- Stream0006.prj (project) ---

Proj Title=Stream0006 Base Level Engineering
Current Plan=p01
Default Exp/Contr=0.3,0.1
English Units
Geom File=g01
Flow File=f01
Plan File=p01
Y Axis Title=Elevation
X Axis Title(PF)=Main Channel Distance
X Axis Title(XS)=Station
BEGIN DESCRIPTION:
Stream0006
END DESCRIPTION:
DSS Export Rating Curves= 0
DSS Export Rating Curve Sorted= 0
DSS Export Volume Flow Curves= 0
DXF OffsetX= 0
DXF OffsetY= 0
DXF ScaleX= 1
DXF ScaleY= 10

--- Stream0006.p01 (plan) ---

Plan Title=Multiple Run
Short Identifier=Multiple
Geom File=g01
Flow File=f01
Subcritical Flow
K Sum by GR= 0
Std Step Tol= 0.01
Critical Tol= 0.01
Num of Std Step Trials= 20
Max Error Tol= 0.3
Flow Tol Ratio= 0.001
Split Flow NTrial= 30
Split Flow Tol= 0.02
Split Flow Ratio= 0.02
Log Output Level= 0
Friction Slope Method= 1
Unsteady Friction Slope Method= 2
Unsteady Bridges Friction Slope Method= 1
Parabolic Critical Depth
Global Vel Dist=  1 , 1 , 1
Global Log Level= 0
CheckData=True
Encroach Param= -1, 0, 0, 0
BEGIN DESCRIPTION:
Multiple Run
END DESCRIPTION:

--- Stream0006.f01 (steady flow) ---

Flow Title=Multiple
Program Version=4.10
Number of Profiles= 7
Profile Names=10-year,25-year,50-year,1pct_min,100-year,1pct_plu,500-year
River Rch & RM=Stream0006,Reach-1         ,653
     495     801    1079     707    1410    2813    2366
Boundary for River Rch & Prof#=Stream0006,Reach-1         , 1
Up Type= 0
Dn Type= 3
Dn Slope=0.008
Boundary for River Rch & Prof#=Stream0006,Reach-1         , 2
Up Type= 0
Dn Type= 3
Dn Slope=0.008
Boundary for River Rch & Prof#=Stream0006,Reach-1         , 3
Up Type= 0
Dn Type= 3
Dn Slope=0.008
Boundary for River Rch & Prof#=Stream0006,Reach-1         , 4
Up Type= 0
Dn Type= 3
Dn Slope=0.008
Boundary for River Rch & Prof#=Stream0006,Reach-1         , 5
Up Type= 0
Dn Type= 3
Dn Slope=0.008
Boundary for River Rch & Prof#=Stream0006,Reach-1         , 6
Up Type= 0
Dn Type= 3
Dn Slope=0.008
Boundary for River Rch & Prof#=Stream0006,Reach-1         , 7
Up Type= 0
Dn Type= 3
Dn Slope=0.008
DSS Import GetInterval= 0
DSS Import GetPeak= 0
DSS Import FillOption= 0

--- Stream0006.g01 (geometry) ---

Geom Title=Existing Conditions

River Reach=Stream0006,Reach-1
Reach XY= 30
      1957225.00     13935625.00      1957345.39     13935505.16
      1957361.37     13935488.20      1957369.14     13935477.26
      1957372.45     13935468.91      1957374.10     13935459.58
      1957376.48     13935435.47      1957378.87     13935426.40
      1957380.74     13935422.42      1957388.46     13935411.37
      1957397.81     13935401.03      1957411.33     13935388.23
      1957418.52     13935382.69      1957422.30     13935380.36
      1957426.25     13935378.45      1957435.28     13935375.99
      1957449.79     13935374.67      1957640.18     13935375.44
      1957654.99     13935374.98      1957664.54     13935373.88
      1957673.51     13935371.40      1957681.16     13935367.11
      1957691.72     13935358.45      1957715.44     13935336.06
      1957722.66     13935330.74      1957726.51     13935328.65
      1957731.27     13935326.99      1957743.20     13935325.12
      1957756.08     13935324.59      1957775.00     13935325.00

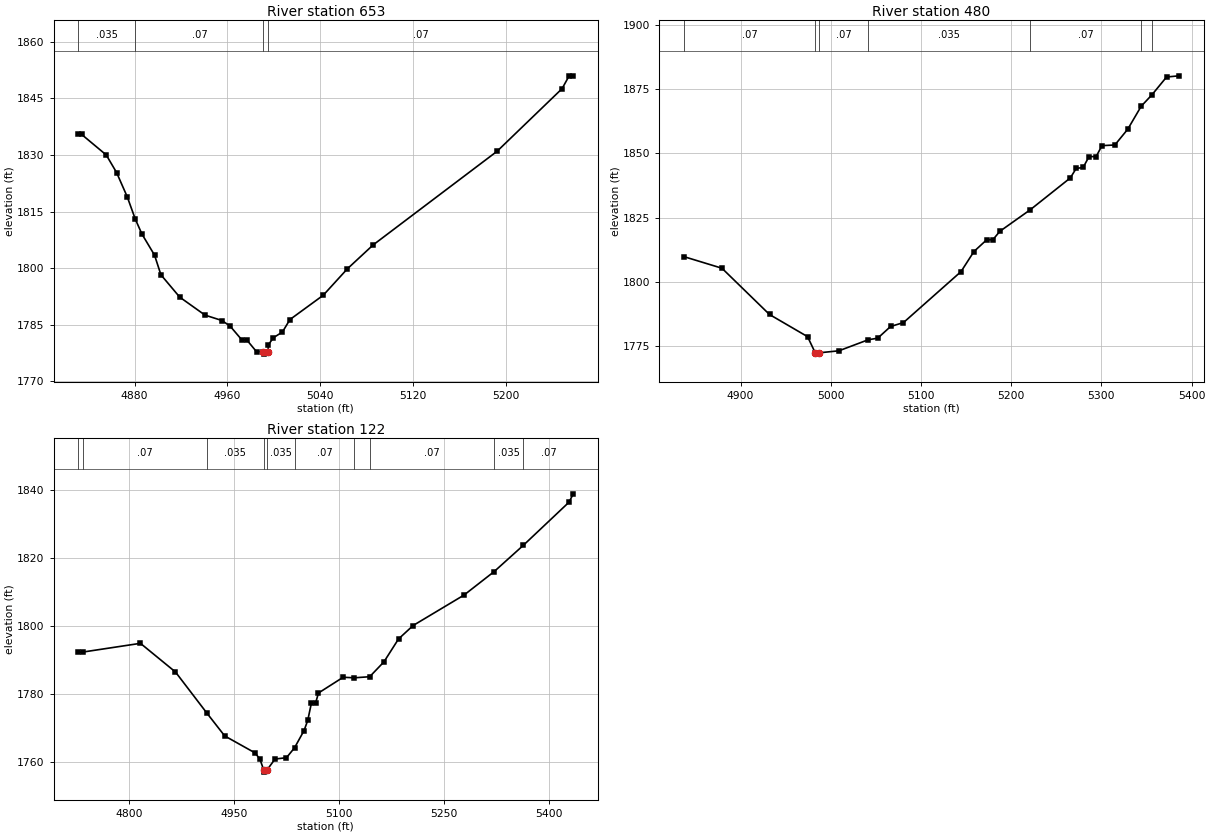
Type RM Length L Ch R = 1,653,173,173,173
BEGIN DESCRIPTION:
Stream0006 2.0
END DESCRIPTION:
XS GIS Cut Line= 3
      1957328.12     13935745.36      1957270.83     13935611.69
      1957054.41     13935432.19
#Sta/Elev= 30
  4831.5 1835.45  4834.4 1835.45  4855.6 1830.01  4864.5 1825.35  4873.7 1818.91
  4880.5 1813.10  4886.3 1809.07  4897.2 1803.46  4902.7 1798.25  4918.9 1792.33
  4940.7 1787.56  4955.3 1786.13  4962.4 1784.62  4972.4 1781.01  4976.9 1780.90
  4985.3 1777.79  4991.1 1777.72  4991.4 1777.22  4995.1 1777.72  4995.2 1779.64
  4999.6 1781.56  5007.4 1783.08  5013.9 1786.39  5042.6 1792.83  5063.4 1799.84
  5085.6 1806.17  5192.4 1830.99  5248.4 1847.59  5254.5 1850.99  5258.1 1850.99
#Mann=4,-1,0
  4831.5   0.035       0  4880.5    0.07       0  4991.1    0.05       0
  4995.1    0.07       0
Bank Sta=4991.1,4995.1
Exp/Cntr=0.3,0.1

Type RM Length L Ch R = 1,480,358,358,358
BEGIN DESCRIPTION:
Stream0006 1.0
END DESCRIPTION:
XS GIS Cut Line= 3
      1957425.01     13935625.04      1957375.00     13935475.00
      1957074.98     13935224.98
#Sta/Elev= 30
  4837.2 1809.88  4879.4 1805.37  4932.1 1787.41  4974.3 1778.80  4982.8 1772.52
  4983.1 1772.02  4986.8 1772.52  5009.0 1773.31  5041.6 1777.61  5052.0 1778.20
  5066.3 1782.75  5080.6 1784.27  5144.4 1804.07  5158.7 1811.86  5173.0 1816.47
  5179.6 1816.41  5187.4 1819.70  5221.1 1828.07  5265.5 1840.43  5272.0 1844.10
  5279.8 1844.53  5286.3 1848.74  5294.1 1848.70  5300.6 1852.97  5314.9 1853.23
  5329.2 1859.36  5344.1 1868.28  5356.0 1872.71  5372.2 1879.62  5385.9 1880.08
#Mann=7,-1,0
  4837.2    0.07       0  4982.8    0.05       0  4986.8    0.07       0
  5041.6   0.035       0  5221.1    0.07       0  5344.1   0.035       0
  5356.0    0.07       0
Bank Sta=4982.8,4986.8
Exp/Cntr=0.3,0.1

Type RM Length L Ch R = 1,122,0,0,0
BEGIN DESCRIPTION:
Stream0006 0.0
END DESCRIPTION:
XS GIS Cut Line= 4
      1957696.06     13935643.48      1957675.69     13935391.44
      1957646.41     13935312.51      1957350.90     13935089.29
#Sta/Elev= 30
  4727.4 1792.19  4734.6 1792.31  4816.2 1794.85  4866.3 1786.43  4910.7 1774.49
  4936.6 1767.67  4980.3 1762.65  4987.1 1760.76  4992.6 1757.54  4992.8 1757.04
  4996.6 1757.54  5008.5 1760.88  5024.9 1761.28  5036.4 1764.18  5050.0 1769.24
  5055.3 1772.24  5060.5 1777.31  5066.5 1777.31  5070.6 1780.27  5105.9 1784.89
  5122.0 1784.73  5143.8 1785.05  5164.2 1789.42  5185.0 1796.13  5205.8 1800.07
  5278.7 1809.03  5321.7 1815.92  5363.4 1823.63  5428.5 1836.26  5434.8 1838.74
#Mann=10,-1,0
  4727.4   0.035       0  4734.6    0.07       0  4910.7   0.035       0
  4992.6   0.035       0  4996.6   0.035       0  5036.4    0.07       0
  5122.0   0.035       0  5143.8    0.07       0  5321.7   0.035       0
  5363.4    0.07       0
Bank Sta=4992.6,4996.6
Exp/Cntr=0.3,0.1

Chan Stop Cuts=-1