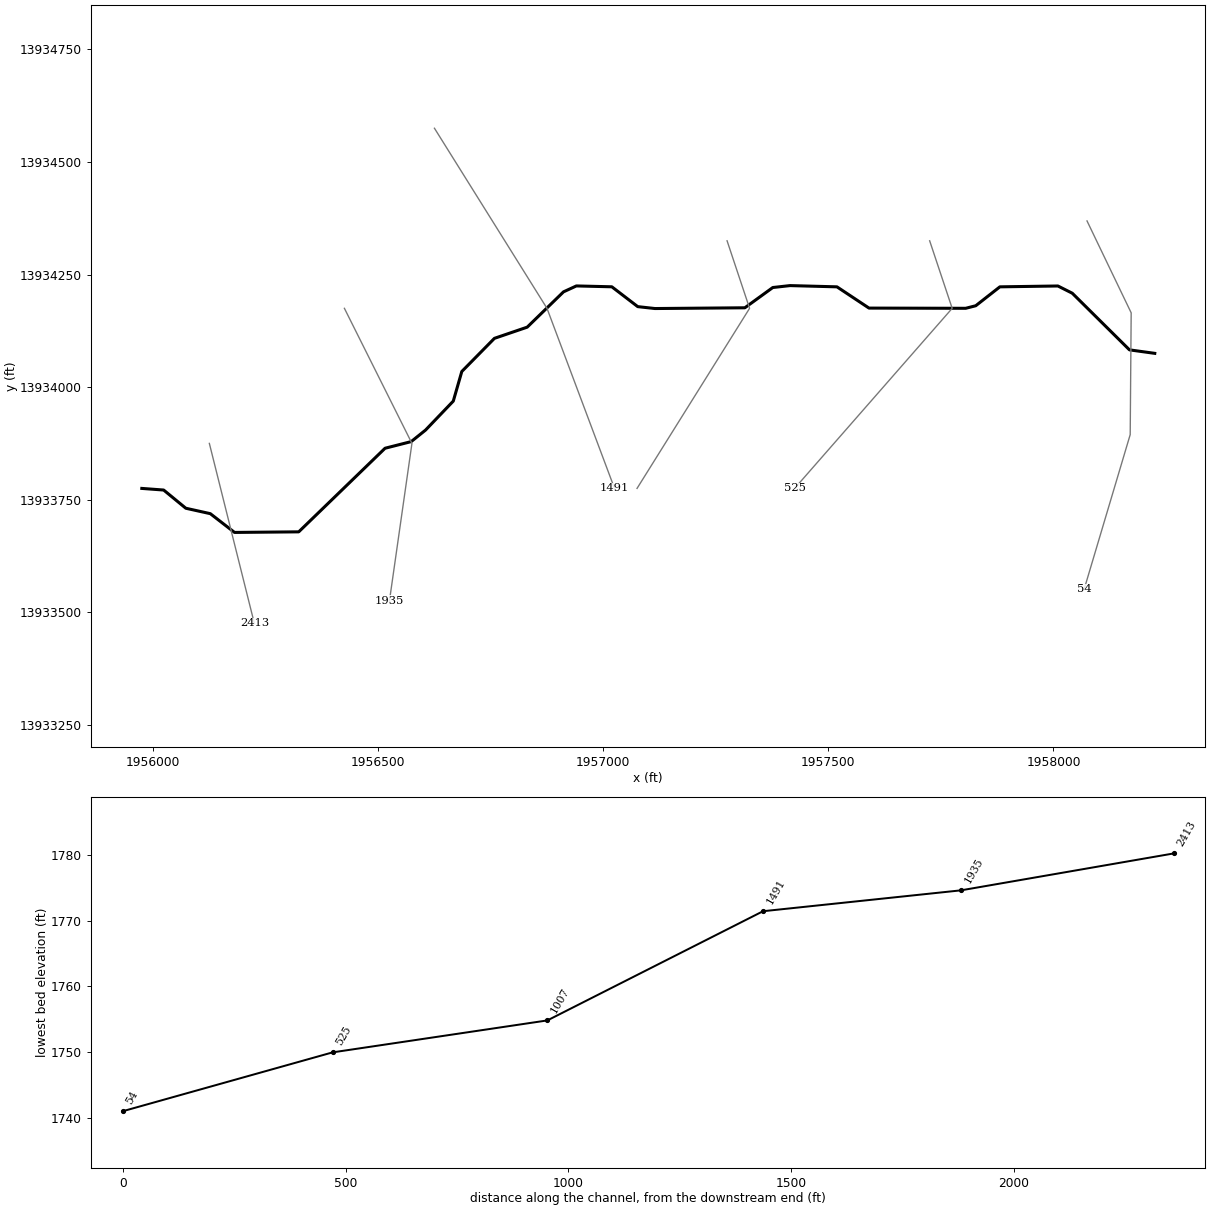
--- Stream0007.prj (project) ---

Proj Title=Stream0007 Base Level Engineering
Current Plan=p01
Default Exp/Contr=0.3,0.1
English Units
Geom File=g01
Flow File=f01
Plan File=p01
BEGIN DESCRIPTION:
Stream0007
END DESCRIPTION:

--- Stream0007.p01 (plan) ---

Plan Title=Multiple Run
Short Identifier=Multiple
Geom File=g01
Flow File=f01
Subcritical Flow
K Sum by GR= 0
Std Step Tol= 0.01
Critical Tol= 0.01
Num of Std Step Trials= 20
Max Error Tol= 0.3
Flow Tol Ratio= 0.001
Split Flow NTrial= 30
Split Flow Tol= 0.02
Split Flow Ratio= 0.02
Log Output Level= 0
Friction Slope Method= 1
Unsteady Friction Slope Method= 2
Unsteady Bridges Friction Slope Method= 1
Parabolic Critical Depth
Global Vel Dist=  1 , 1 , 1
Global Log Level= 0
CheckData=True
Encroach Param= -1, 0, 0, 0
BEGIN DESCRIPTION:
Multiple Run
END DESCRIPTION:

--- Stream0007.f01 (steady flow) ---

Flow Title=Multiple
Number of Profiles=7
Profile Names=10-year,25-year,50-year,1pct_min,100-year,1pct_plu,500-year
River Rch & RM= Stream0007,Reach-1,2413
    1726    3008    4256    2908    5802   11576   10647
Boundary for River Rch & Prof#=Stream0007,Reach-1,1
Up Type=0
Dn Type=3
Dn Slope=0.005
Boundary for River Rch & Prof#=Stream0007,Reach-1,2
Up Type=0
Dn Type=3
Dn Slope=0.005
Boundary for River Rch & Prof#=Stream0007,Reach-1,3
Up Type=0
Dn Type=3
Dn Slope=0.005
Boundary for River Rch & Prof#=Stream0007,Reach-1,4
Up Type=0
Dn Type=3
Dn Slope=0.005
Boundary for River Rch & Prof#=Stream0007,Reach-1,5
Up Type=0
Dn Type=3
Dn Slope=0.005
Boundary for River Rch & Prof#=Stream0007,Reach-1,6
Up Type=0
Dn Type=3
Dn Slope=0.005
Boundary for River Rch & Prof#=Stream0007,Reach-1,7
Up Type=0
Dn Type=3
Dn Slope=0.005

--- Stream0007.g01 (geometry) ---

Geom Title=Existing Conditions

River Reach=Stream0007,Reach-1
Reach XY= 30
      1955975.00     13933775.00      1956023.51     13933771.40
      1956072.75     13933730.95      1956127.19     13933718.89
      1956180.93     13933677.23      1956323.53     13933678.53
      1956515.32     13933864.22      1956573.36     13933878.97
      1956605.23     13933904.58      1956666.85     13933968.94
      1956685.77     13934034.70      1956758.29     13934108.36
      1956831.04     13934133.18      1956911.71     13934211.64
      1956940.22     13934224.75      1957019.02     13934222.84
      1957076.56     13934178.78      1957114.81     13934174.55
      1957314.50     13934176.22      1957376.57     13934221.23
      1957414.83     13934225.50      1957519.06     13934222.75
      1957590.22     13934175.52      1957804.97     13934175.07
      1957827.33     13934180.75      1957880.94     13934222.75
      1958009.84     13934224.64      1958041.76     13934208.57
      1958168.79     13934082.76      1958225.00     13934075.00

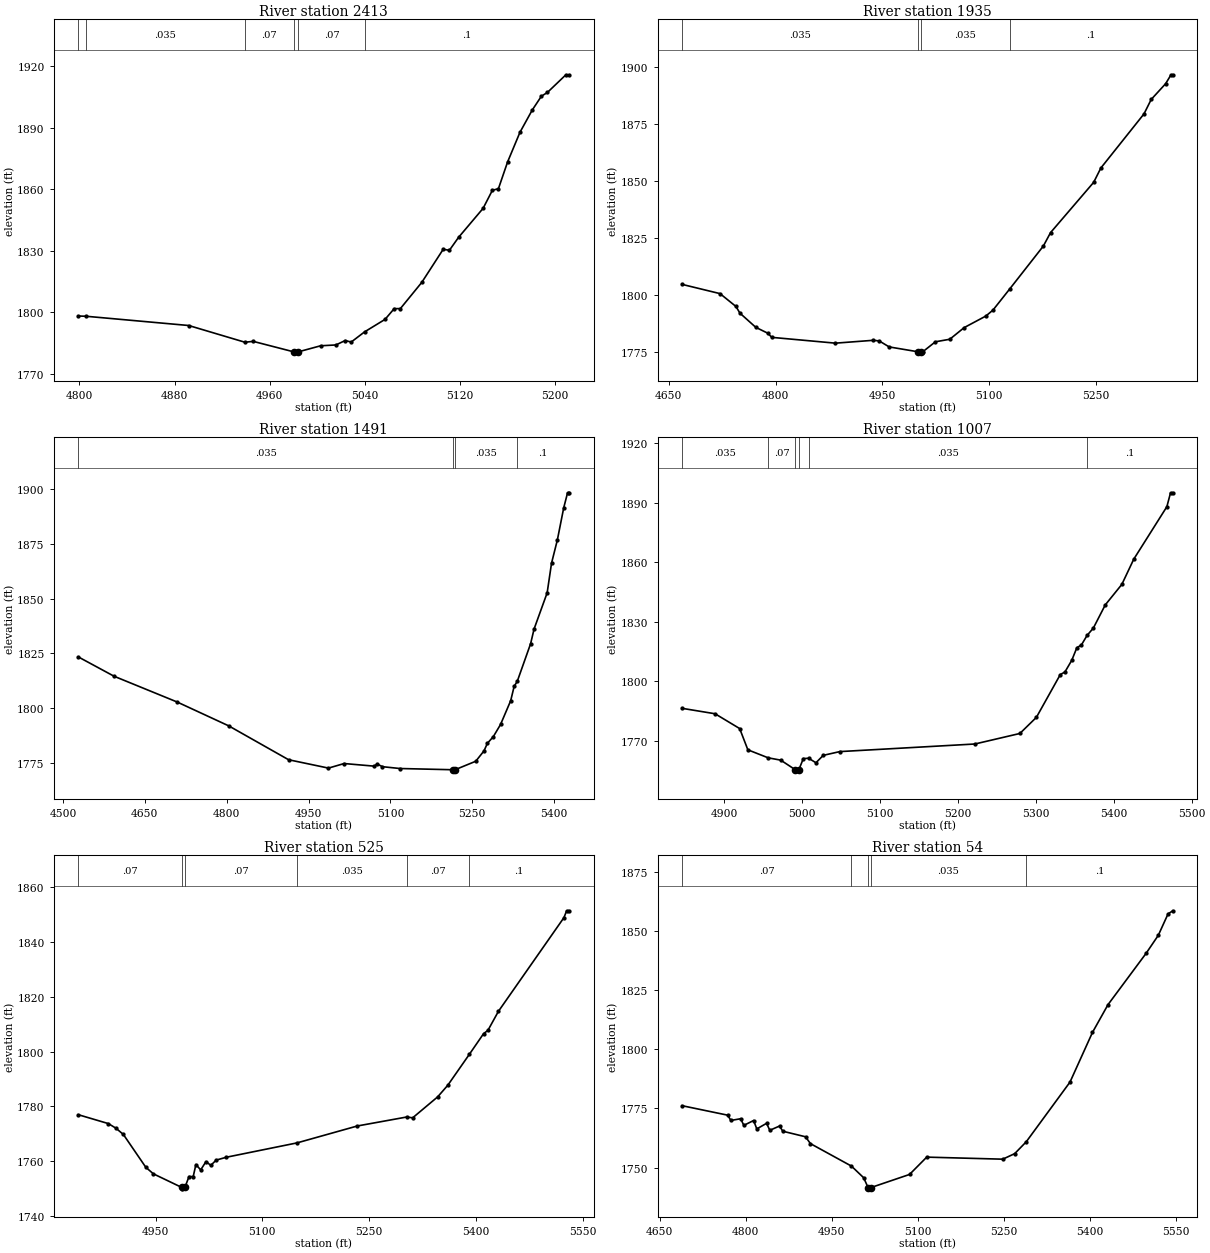
Type RM Length L Ch R = 1,2413,478,478,478
BEGIN DESCRIPTION:
Stream0007 5.0
END DESCRIPTION:
XS GIS Cut Line= 3
      1956125.01     13933874.98      1956175.00     13933675.00
      1956225.00     13933474.99
#Sta/Elev= 30
  4799.2 1798.20  4805.5 1798.09  4891.9 1793.58  4939.2 1785.42  4946.1 1785.85
  4980.1 1780.76  4980.4 1780.26  4984.1 1780.76  5002.8 1783.70  5015.6 1784.10
  5023.4 1786.25  5028.5 1785.52  5039.7 1790.47  5056.9 1796.56  5064.6 1801.79
  5069.8 1801.82  5087.8 1814.60  5105.8 1830.73  5111.0 1830.23  5118.7 1836.53
  5139.3 1850.65  5147.1 1859.45  5152.2 1860.25  5159.9 1873.27  5170.3 1887.73
  5180.6 1898.55  5188.3 1905.30  5193.4 1907.16  5208.9 1915.75  5211.5 1915.75
#Mann=6,-1,0
  4799.2    0.07       0  4805.5   0.035       0  4939.2    0.07       0
  4980.1    0.05       0  4984.1    0.07       0  5039.7     0.1       0
Bank Sta=4980.1,4984.1
Exp/Cntr=0.3,0.1

Type RM Length L Ch R = 1,1935,444,444,444
BEGIN DESCRIPTION:
Stream0007 4.0
END DESCRIPTION:
XS GIS Cut Line= 3
      1956424.99     13934175.02      1956575.00     13933875.00
      1956525.00     13933524.98
#Sta/Elev= 30
  4668.9 1804.60  4722.0 1800.57  4744.4 1794.94  4750.0 1792.01  4772.3 1785.79
  4789.1 1783.23  4794.7 1781.41  4884.1 1778.87  4937.2 1780.12  4945.6 1779.85
  4959.6 1777.22  4999.4 1775.13  4999.7 1774.63  5003.6 1775.13  5006.9 1775.13
  5024.5 1779.47  5044.7 1780.58  5064.9 1785.68  5095.2 1790.72  5105.3 1793.33
  5128.8 1802.58  5176.1 1821.40  5186.2 1827.28  5246.8 1849.32  5256.9 1855.60
  5317.5 1879.31  5327.6 1885.63  5347.8 1892.50  5355.4 1896.42  5357.9 1896.42
#Mann=4,-1,0
  4668.9   0.035       0  4999.4   0.035       0  5003.6   0.035       0
  5128.8     0.1       0
Bank Sta=4999.4,5003.6
Exp/Cntr=0.3,0.1

Type RM Length L Ch R = 1,1491,484,484,484
BEGIN DESCRIPTION:
Stream0007 3.0
END DESCRIPTION:
XS GIS Cut Line= 3
      1956624.98     13934575.04      1956875.00     13934175.00
      1957024.98     13933775.04
#Sta/Elev= 30
  4528.3 1823.41  4593.8 1814.60  4709.4 1802.84  4803.7 1791.98  4913.4 1776.52
  4986.5 1772.70  5015.2 1774.78  5070.4 1773.59  5075.7 1774.56  5085.5 1773.34
  5117.5 1772.51  5214.2 1771.95  5214.5 1771.45  5218.4 1771.95  5256.4 1775.83
  5271.5 1780.56  5277.7 1784.02  5288.4 1786.99  5301.8 1792.60  5320.4 1803.46
  5326.7 1809.98  5332.4 1812.27  5356.9 1829.47  5363.2 1836.14  5387.2 1852.68
  5395.2 1866.16  5405.9 1876.80  5417.5 1891.41  5424.6 1898.32  5427.2 1898.32
#Mann=4,-1,0
  4528.3   0.035       0  5214.2   0.035       0  5218.4   0.035       0
  5332.4     0.1       0
Bank Sta=5214.2,5218.4
Exp/Cntr=0.3,0.1

Type RM Length L Ch R = 1,1007,482,482,482
BEGIN DESCRIPTION:
Stream0007 2.0
END DESCRIPTION:
XS GIS Cut Line= 3
      1957275.00     13934325.01      1957325.00     13934175.00
      1957075.01     13933775.02
#Sta/Elev= 30
  4846.0 1786.32  4888.2 1783.59  4919.8 1776.12  4930.3 1765.41  4956.4 1761.37
  4972.5 1760.20  4991.4 1755.31  4991.7 1754.81  4995.7 1755.31  5001.5 1760.99
  5008.4 1761.15  5017.7 1758.88  5027.1 1762.62  5048.3 1764.51  5221.7 1768.34
  5279.5 1773.65  5300.7 1781.78  5331.4 1803.37  5337.3 1804.64  5346.1 1810.54
  5352.6 1816.86  5358.5 1818.30  5365.8 1823.11  5373.8 1826.78  5389.1 1838.47
  5410.4 1848.82  5425.7 1861.54  5468.2 1888.00  5472.9 1895.01  5475.8 1895.01
#Mann=6,-1,0
  4846.0   0.035       0  4956.4    0.07       0  4991.4    0.05       0
  4995.7    0.07       0  5008.4   0.035       0  5365.8     0.1       0
Bank Sta=4991.4,4995.7
Exp/Cntr=0.3,0.1

Type RM Length L Ch R = 1,525,471,471,471
BEGIN DESCRIPTION:
Stream0007 1.0
END DESCRIPTION:
XS GIS Cut Line= 3
      1957725.01     13934324.98      1957775.00     13934175.00
      1957425.00     13933775.00
#Sta/Elev= 30
  4841.4 1776.99  4883.5 1773.76  4894.1 1772.09  4904.6 1769.80  4936.2 1757.80
  4946.8 1755.42  4986.8 1750.44  4987.1 1749.94  4991.1 1750.44  4996.9 1754.42
  5002.8 1754.42  5006.6 1758.81  5013.3 1756.85  5020.8 1759.89  5027.5 1758.51
  5035.1 1760.43  5049.3 1761.47  5148.7 1766.71  5233.4 1772.88  5302.7 1776.15
  5311.3 1775.87  5346.4 1783.51  5360.6 1787.74  5390.9 1799.02  5410.9 1806.57
  5417.1 1807.81  5431.8 1814.73  5523.9 1848.94  5527.7 1851.44  5531.0 1851.44
#Mann=6,-1,0
  4841.4    0.07       0  4986.8    0.05       0  4991.1    0.07       0
  5148.7   0.035       0  5302.7    0.07       0  5390.9     0.1       0
Bank Sta=4986.8,4991.1
Exp/Cntr=0.3,0.1

Type RM Length L Ch R = 1,54,0,0,0
BEGIN DESCRIPTION:
Stream0007 0.0
END DESCRIPTION:
XS GIS Cut Line= 4
      1958074.52     13934369.14      1958172.60     13934165.00
      1958170.43     13933894.49      1958068.05     13933550.71
#Sta/Elev= 30
  4689.2 1776.17  4768.5 1772.17  4774.1 1769.93  4791.2 1770.66  4796.7 1767.85
  4813.8 1769.91  4819.3 1766.35  4836.4 1768.72  4842.0 1765.76  4859.1 1767.58
  4864.6 1765.37  4904.3 1763.02  4912.9 1760.12  4984.4 1750.60  5005.7 1745.67
  5013.5 1741.47  5013.8 1740.97  5017.9 1741.47  5085.7 1747.06  5115.7 1754.40
  5248.3 1753.53  5269.1 1755.87  5289.3 1760.90  5365.6 1786.18  5404.8 1807.22
  5431.9 1818.98  5498.2 1840.66  5519.6 1848.33  5536.6 1857.41  5544.9 1858.73
#Mann=5,-1,0
  4689.2    0.07       0  4984.4   0.035       0  5013.5   0.035       0
  5017.9   0.035       0  5289.3     0.1       0
Bank Sta=5013.5,5017.9
Exp/Cntr=0.3,0.1

Chan Stop Cuts=-1