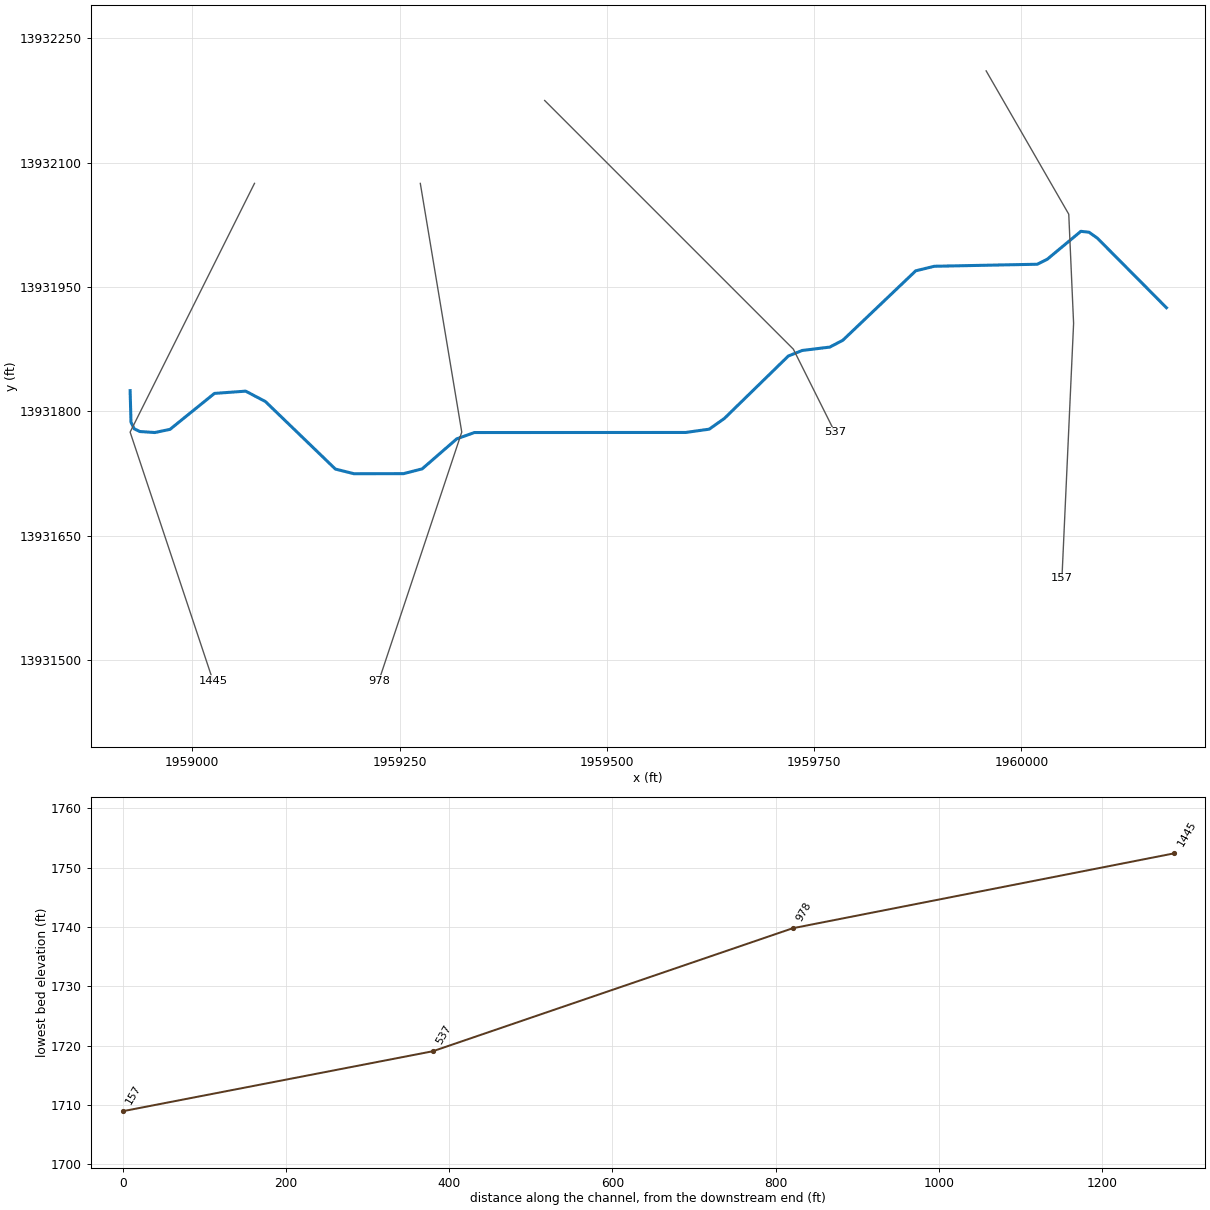
--- Stream0008.prj (project) ---

Proj Title=Stream0008 Base Level Engineering
Current Plan=p01
Default Exp/Contr=0.3,0.1
English Units
Geom File=g01
Flow File=f01
Plan File=p01
BEGIN DESCRIPTION:
Stream0008
END DESCRIPTION:

--- Stream0008.p01 (plan) ---

Plan Title=Multiple Run
Short Identifier=Multiple
Geom File=g01
Flow File=f01
Subcritical Flow
K Sum by GR= 0
Std Step Tol= 0.01
Critical Tol= 0.01
Num of Std Step Trials= 20
Max Error Tol= 0.3
Flow Tol Ratio= 0.001
Split Flow NTrial= 30
Split Flow Tol= 0.02
Split Flow Ratio= 0.02
Log Output Level= 0
Friction Slope Method= 1
Unsteady Friction Slope Method= 2
Unsteady Bridges Friction Slope Method= 1
Parabolic Critical Depth
Global Vel Dist=  1 , 1 , 1
Global Log Level= 0
CheckData=True
Encroach Param= -1, 0, 0, 0
BEGIN DESCRIPTION:
Multiple Run
END DESCRIPTION:

--- Stream0008.f01 (steady flow) ---

Flow Title=Multiple
Number of Profiles=7
Profile Names=10-year,25-year,50-year,1pct_min,100-year,1pct_plu,500-year
River Rch & RM= Stream0008,Reach-1,1445
     570     935    1271     840    1676    3344    2865
Boundary for River Rch & Prof#=Stream0008,Reach-1,1
Up Type=0
Dn Type=3
Dn Slope=0.005
Boundary for River Rch & Prof#=Stream0008,Reach-1,2
Up Type=0
Dn Type=3
Dn Slope=0.005
Boundary for River Rch & Prof#=Stream0008,Reach-1,3
Up Type=0
Dn Type=3
Dn Slope=0.005
Boundary for River Rch & Prof#=Stream0008,Reach-1,4
Up Type=0
Dn Type=3
Dn Slope=0.005
Boundary for River Rch & Prof#=Stream0008,Reach-1,5
Up Type=0
Dn Type=3
Dn Slope=0.005
Boundary for River Rch & Prof#=Stream0008,Reach-1,6
Up Type=0
Dn Type=3
Dn Slope=0.005
Boundary for River Rch & Prof#=Stream0008,Reach-1,7
Up Type=0
Dn Type=3
Dn Slope=0.005

--- Stream0008.g01 (geometry) ---

Geom Title=Existing Conditions

River Reach=Stream0008,Reach-1
Reach XY= 30
      1958925.00     13931825.00      1958926.04     13931786.95
      1958929.90     13931778.98      1958936.73     13931775.71
      1958954.72     13931774.48      1958973.09     13931778.30
      1959026.71     13931821.67      1959064.37     13931824.40
      1959088.20     13931811.85      1959172.58     13931730.41
      1959195.05     13931724.79      1959254.90     13931724.90
      1959277.31     13931730.68      1959318.94     13931766.85
      1959340.22     13931774.48      1959595.18     13931774.57
      1959623.53     13931778.55      1959641.75     13931791.46
      1959718.96     13931866.82      1959735.64     13931873.45
      1959768.95     13931877.54      1959784.67     13931885.80
      1959872.56     13931969.52      1959894.99     13931975.02
      1960019.15     13931977.47      1960031.19     13931983.47
      1960071.79     13932017.19      1960081.74     13932016.01
      1960091.71     13932008.90      1960175.00     13931925.00

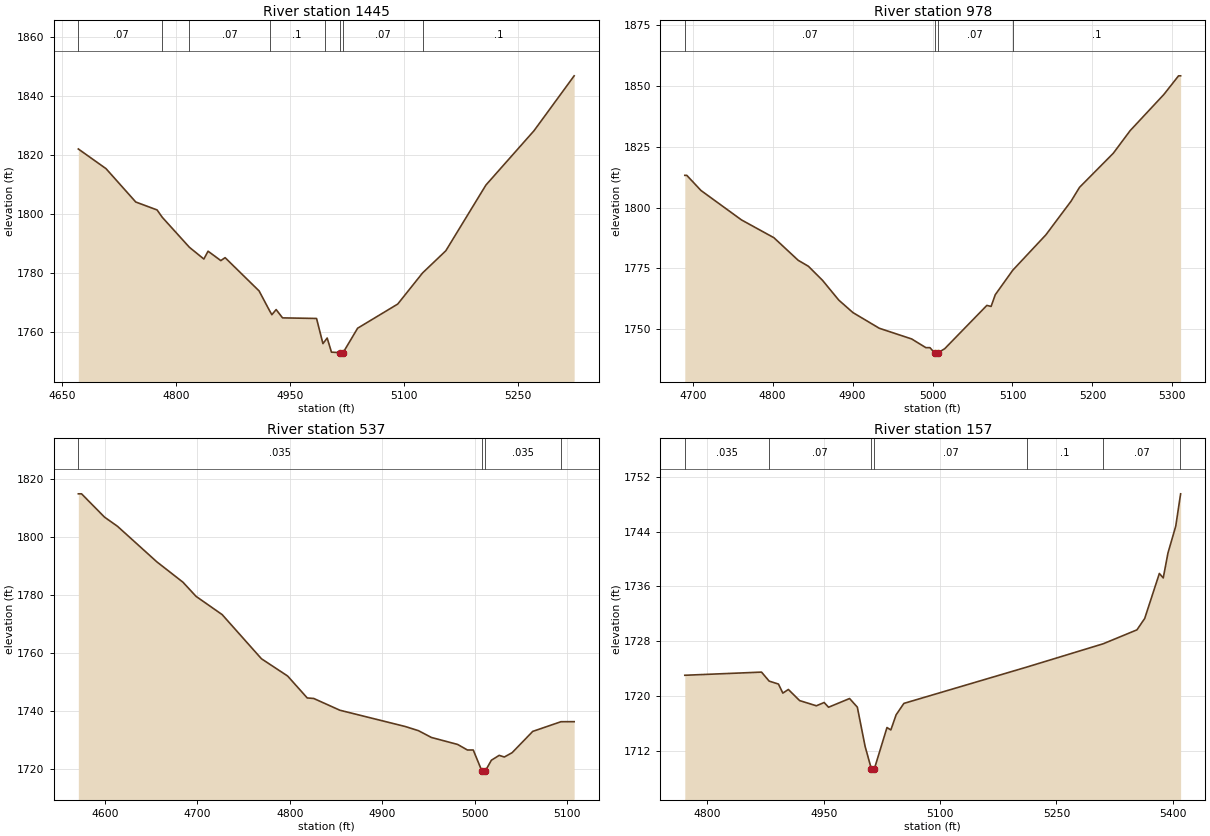
Type RM Length L Ch R = 1,1445,467,467,467
BEGIN DESCRIPTION:
Stream0008 3.0
END DESCRIPTION:
XS GIS Cut Line= 3
      1959075.02     13932075.04      1958925.00     13931775.00
      1959025.00     13931474.99
#Sta/Elev= 30
  4671.7 1822.04  4708.1 1815.36  4747.2 1804.03  4775.2 1801.34  4782.1 1798.82
  4817.7 1788.66  4836.7 1784.67  4842.2 1787.33  4859.0 1784.14  4864.6 1785.14
  4909.3 1773.84  4923.1 1767.11  4926.1 1765.76  4931.7 1767.51  4940.1 1764.69
  4984.8 1764.49  4993.2 1755.95  4995.7 1756.79  4998.8 1757.84  5004.4 1753.05
  5015.7 1752.88  5015.9 1752.38  5019.7 1752.88  5038.8 1761.18  5091.5 1769.38
  5124.2 1779.96  5154.7 1787.47  5207.4 1809.78  5270.7 1828.26  5323.4 1846.88
#Mann=8,-1,0
  4671.7    0.07       0  4782.1     0.1       0  4817.7    0.07       0
  4923.1     0.1       0  4995.7    0.07       0  5015.7    0.05       0
  5019.7    0.07       0  5124.2     0.1       0
Bank Sta=5015.7,5019.7
Exp/Cntr=0.3,0.1

Type RM Length L Ch R = 1,978,441,441,441
BEGIN DESCRIPTION:
Stream0008 2.0
END DESCRIPTION:
XS GIS Cut Line= 3
      1959275.01     13932074.97      1959325.00     13931775.00
      1959225.01     13931475.03
#Sta/Elev= 30
  4690.1 1813.23  4692.6 1813.23  4710.3 1807.02  4761.0 1794.92  4801.6 1787.60
  4832.0 1778.31  4844.7 1775.88  4862.4 1770.09  4882.7 1761.98  4900.4 1756.85
  4933.4 1750.40  4973.9 1746.01  4991.7 1742.43  4996.8 1742.43  5002.7 1740.27
  5003.0 1739.77  5006.7 1740.27  5015.3 1742.01  5068.0 1759.79  5073.3 1759.37
  5078.5 1764.17  5100.3 1774.21  5141.8 1788.77  5173.4 1802.64  5183.9 1808.29
  5226.1 1822.28  5247.2 1831.58  5289.4 1846.44  5307.8 1854.12  5310.4 1854.12
#Mann=4,-1,0
  4690.1    0.07       0  5002.7    0.05       0  5006.7    0.07       0
  5100.3     0.1       0
Bank Sta=5002.7,5006.7
Exp/Cntr=0.3,0.1

Type RM Length L Ch R = 1,537,380,380,380
BEGIN DESCRIPTION:
Stream0008 1.0
END DESCRIPTION:
XS GIS Cut Line= 3
      1959425.01     13932174.99      1959725.00     13931875.00
      1959775.02     13931774.96
#Sta/Elev= 30
  4571.4 1815.00  4574.9 1815.00  4599.7 1806.97  4613.8 1803.79  4656.2 1791.57
  4684.5 1784.53  4698.7 1779.64  4726.9 1773.36  4769.4 1758.13  4797.7 1752.18
  4818.9 1744.62  4825.9 1744.44  4854.2 1740.38  4924.9 1734.77  4939.1 1733.34
  4953.2 1730.99  4981.5 1728.59  4992.1 1726.67  4998.4 1726.67  5007.6 1719.54
  5007.9 1719.04  5011.4 1719.04  5011.6 1719.54  5018.0 1723.14  5026.4 1724.82
  5032.0 1724.26  5040.4 1725.73  5062.7 1733.08  5093.2 1736.42  5107.5 1736.44
#Mann=4,-1,0
  4571.4   0.035       0  5007.6   0.035       0  5011.6   0.035       0
  5093.2    0.07       0
Bank Sta=5007.6,5011.6
Exp/Cntr=0.3,0.1

Type RM Length L Ch R = 1,157,0,0,0
BEGIN DESCRIPTION:
Stream0008 0.0
END DESCRIPTION:
XS GIS Cut Line= 4
      1959957.52     13932210.70      1960057.16     13932037.82
      1960062.99     13931906.07      1960048.93     13931598.71
#Sta/Elev= 30
  4770.9 1723.05  4869.8 1723.51  4879.6 1722.20  4891.6 1721.77  4897.3 1720.45
  4904.4 1720.98  4918.9 1719.36  4940.5 1718.60  4950.5 1719.08  4956.2 1718.39
  4983.3 1719.66  4993.3 1718.40  5003.3 1712.69  5011.3 1709.43  5011.6 1708.93
  5015.3 1709.43  5031.5 1715.43  5036.5 1715.08  5043.3 1717.29  5053.3 1718.95
  5211.6 1724.24  5310.2 1727.64  5353.7 1729.67  5363.7 1731.33  5382.6 1737.89
  5387.6 1737.24  5393.7 1740.88  5403.7 1744.78  5408.8 1748.60  5410.0 1749.50
#Mann=7,-1,0
  4770.9   0.035       0  4879.6    0.07       0  5011.3    0.05       0
  5015.3    0.07       0  5211.6     0.1       0  5310.2    0.07       0
  5408.8     0.1       0
Bank Sta=5011.3,5015.3
Exp/Cntr=0.3,0.1

Chan Stop Cuts=-1