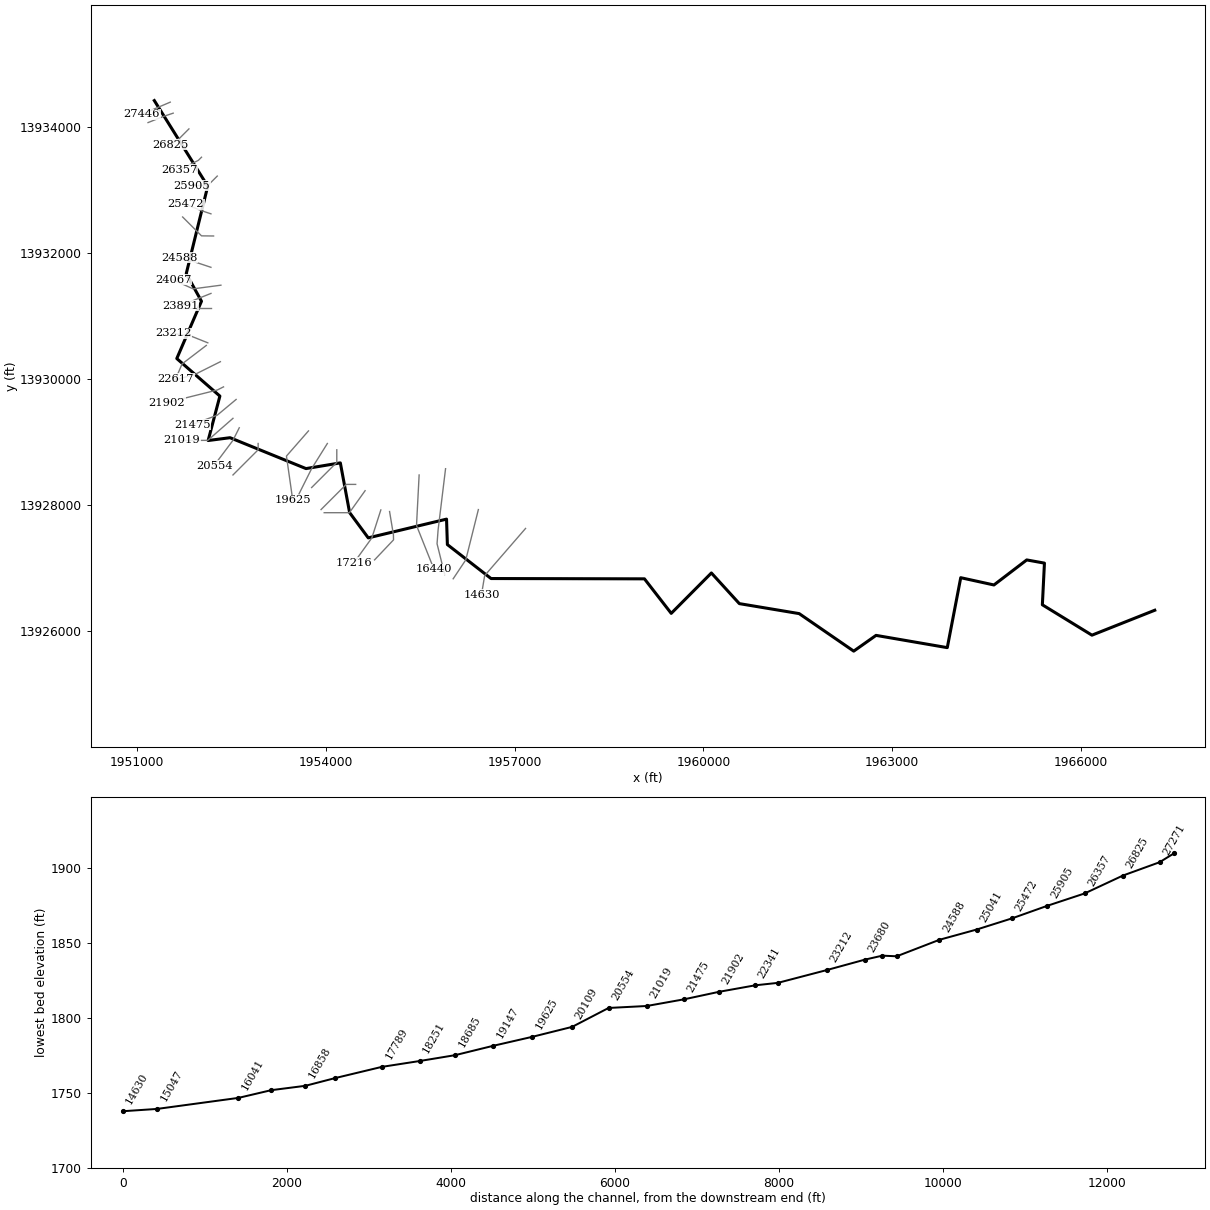
--- Stream0009.prj (project) ---

Proj Title=Stream0009 Base Level Engineering
Current Plan=p01
Default Exp/Contr=0.3,0.1
English Units
Geom File=g01
Flow File=f01
Plan File=p01
Y Axis Title=Elevation
X Axis Title(PF)=Main Channel Distance
X Axis Title(XS)=Station
BEGIN DESCRIPTION:
Stream0009
END DESCRIPTION:
DSS Export Rating Curves= 0
DSS Export Rating Curve Sorted= 0
DSS Export Volume Flow Curves= 0
DXF OffsetX= 0
DXF OffsetY= 0
DXF ScaleX= 1
DXF ScaleY= 10

--- Stream0009.p01 (plan) ---

Plan Title=Multiple Run
Short Identifier=Multiple
Geom File=g01
Flow File=f01
Subcritical Flow
K Sum by GR= 0
Std Step Tol= 0.01
Critical Tol= 0.01
Num of Std Step Trials= 20
Max Error Tol= 0.3
Flow Tol Ratio= 0.001
Split Flow NTrial= 30
Split Flow Tol= 0.02
Split Flow Ratio= 0.02
Log Output Level= 0
Friction Slope Method= 1
Unsteady Friction Slope Method= 2
Unsteady Bridges Friction Slope Method= 1
Parabolic Critical Depth
Global Vel Dist=  1 , 1 , 1
Global Log Level= 0
CheckData=True
Encroach Param= -1, 0, 0, 0
BEGIN DESCRIPTION:
Multiple Run
END DESCRIPTION:

--- Stream0009.f01 (steady flow) ---

Flow Title=Multiple
Number of Profiles=7
Profile Names=10-year,25-year,50-year,1pct_min,100-year,1pct_plu,500-year
River Rch & RM= Stream0009,Reach-1,27446
     731    1209    1651    1093    2181    4352    3749
River Rch & RM= Stream0009,Reach-1,24588
    1022    1725    2387    1599    3191    6367    5623
River Rch & RM= Stream0009,Reach-1,22617
    2012    3524    5000    3424    6832   13631   12596
River Rch & RM= Stream0009,Reach-1,17216
    2614    4639    6643    4585    9149   18255   17148
River Rch & RM= Stream0009,Reach-1,15047
    3153    5640    8116    5626   11225   22397   21223
River Rch & RM= Stream0009,Reach-1,10947
    3875    6982   10097    7028   14022   27978   26730
River Rch & RM= Stream0009,Reach-1,4433
    4036    7280   10535    7335   14636   29202   27924
River Rch & RM= Stream0009,Reach-1,1374
    4275    7728   11200    7809   15581   31088   29807
Boundary for River Rch & Prof#=Stream0009,Reach-1,1
Up Type=0
Dn Type=3
Dn Slope=0.005
Boundary for River Rch & Prof#=Stream0009,Reach-1,2
Up Type=0
Dn Type=3
Dn Slope=0.005
Boundary for River Rch & Prof#=Stream0009,Reach-1,3
Up Type=0
Dn Type=3
Dn Slope=0.005
Boundary for River Rch & Prof#=Stream0009,Reach-1,4
Up Type=0
Dn Type=3
Dn Slope=0.005
Boundary for River Rch & Prof#=Stream0009,Reach-1,5
Up Type=0
Dn Type=3
Dn Slope=0.005
Boundary for River Rch & Prof#=Stream0009,Reach-1,6
Up Type=0
Dn Type=3
Dn Slope=0.005
Boundary for River Rch & Prof#=Stream0009,Reach-1,7
Up Type=0
Dn Type=3
Dn Slope=0.005

--- Stream0009.g01 (geometry) ---

Geom Title=Existing Conditions
Program Version=4.10

River Reach=Stream0009      ,Reach-1
Reach XY= 30
        1951275.       13934425.      1952123.95     13933064.56
      1951782.56       13931675.      1952024.44     13931235.64
      1951632.05     13930325.07      1952316.96     13929728.32
      1952130.34     13929022.26      1952478.31     13929066.98
      1953685.55      13928576.1      1954231.38       13928667.
      1954378.75     13927876.55        1954675.       13927475.
      1955919.16     13927772.95      1955932.59     13927368.37
      1956626.55     13926828.75      1959064.57     13926823.97
      1959490.16     13926275.34      1960128.42     13926917.21
       1960572.7     13926430.09      1961523.53     13926271.44
      1962390.47     13925674.99      1962745.13     13925925.39
      1963877.44     13925730.52      1964091.24     13926842.23
      1964618.96     13926726.61      1965140.21     13927124.49
      1965421.57     13927073.78      1965388.62     13926411.78
      1966176.55     13925928.75        1967175.       13926325.

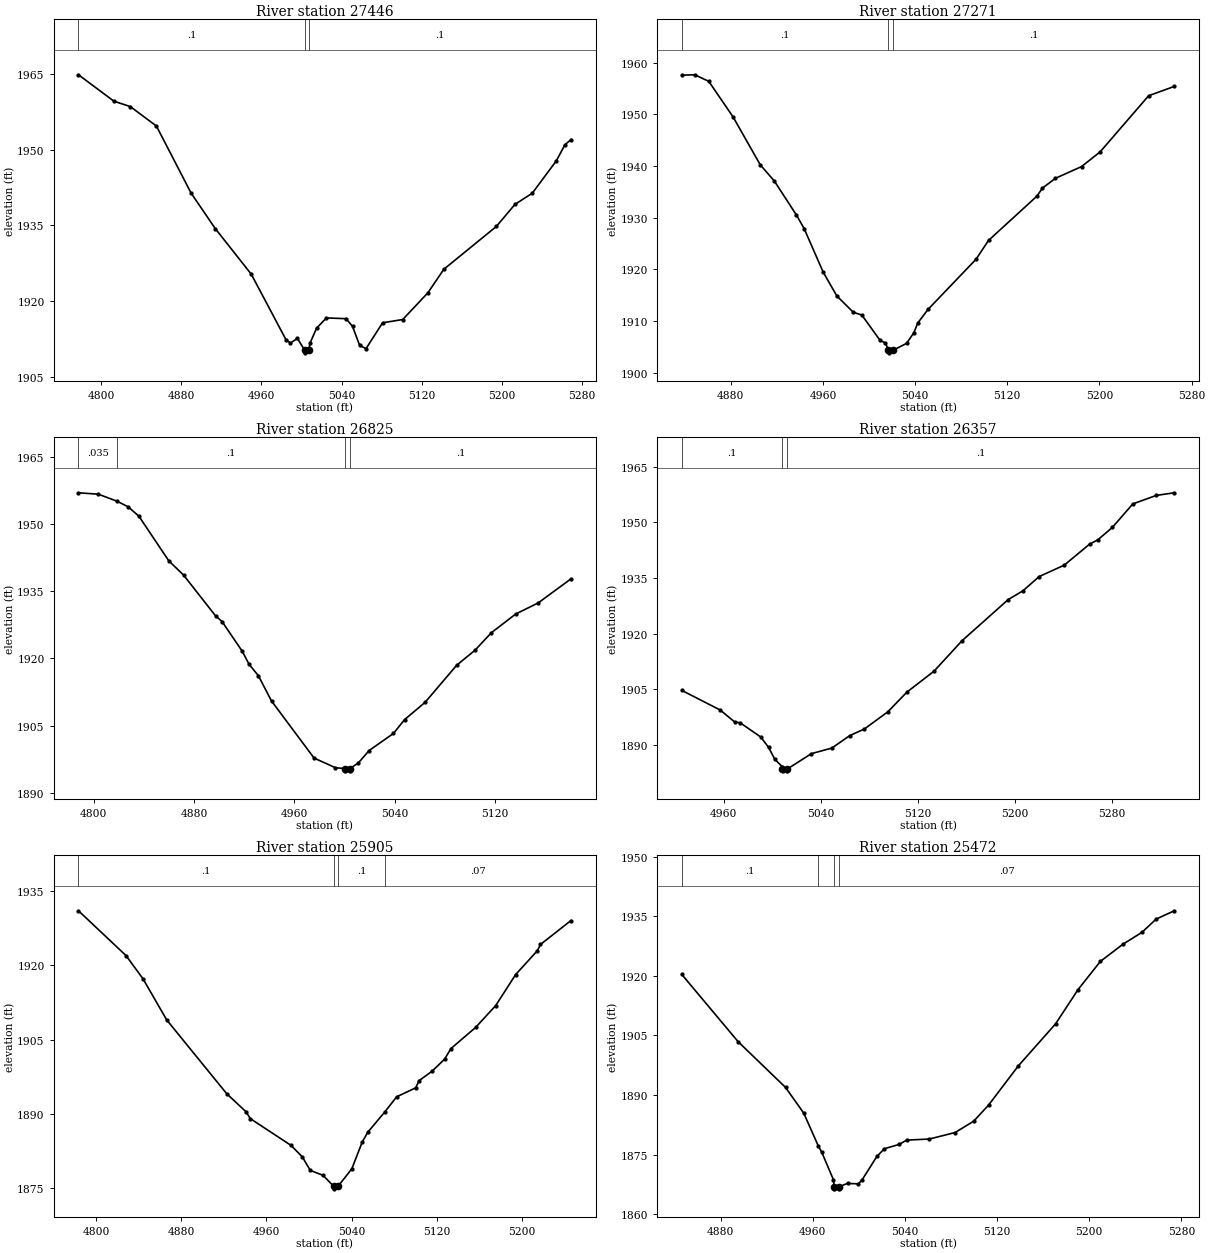
Type RM Length L Ch R = 1 ,27446   ,175,175,175
BEGIN DESCRIPTION:
Stream0009 57.0
END DESCRIPTION:
XS GIS Cut Line= 2
      1951528.29     13934400.17      1951076.23     13934207.26
#Sta/Elev= 30
  4777.4 1964.84  4812.8  1959.6  4829.1 1958.54  4855.2 1954.68  4889.8 1941.39
  4913.9 1934.36  4949.8 1925.33  4984.4 1912.37  4988.9 1911.67  4995.9 1912.59
  5003.2 1910.23  5003.5 1909.73  5007.2 1910.23  5008.5 1911.66    5015 1914.61
  5024.8 1916.65  5044.4  1916.5  5050.9 1914.99    5058  1911.2  5064.4 1910.57
  5080.9 1915.69    5101 1916.33  5126.2 1921.65    5142 1926.29  5194.4 1934.77
    5213 1939.15  5230.3 1941.37  5254.2 1947.76  5262.9 1950.98  5268.9 1951.99
#Mann= 3 ,-1 , 0
  4777.4      .1       0  5003.2     .05       0  5007.2      .1       0
Bank Sta=5003.2,5007.2
XS Rating Curve= 0 ,0
Exp/Cntr=0.3,0.1

Type RM Length L Ch R = 1 ,27271   ,446,446,446
BEGIN DESCRIPTION:
Stream0009 56.0
END DESCRIPTION:
XS GIS Cut Line= 3
      1951574.97     13934224.99        1951425.       13934175.
      1951175.04     13934075.02
#Sta/Elev= 30
  4837.6 1957.56  4848.8 1957.64    4861 1956.37    4882 1949.51  4905.7  1940.2
  4917.9 1937.08  4936.9 1930.55  4943.7 1927.89  4960.3 1919.43  4972.1 1914.84
  4986.4 1911.68  4993.8 1911.14  5009.7 1906.22  5014.3 1905.74  5016.9 1904.33
  5017.2 1903.83  5020.9 1904.33  5032.6 1905.66    5039 1907.74  5042.3 1909.59
  5051.2 1912.23  5092.8 1921.92  5103.7 1925.58  5145.7 1934.15  5150.5 1935.71
  5161.8 1937.61  5184.4 1939.87  5200.6 1942.73  5242.6 1953.58  5264.9 1955.39
#Mann= 3 ,-1 , 0
  4837.6      .1       0  5016.9     .05       0  5020.9      .1       0
Bank Sta=5016.9,5020.9
XS Rating Curve= 0 ,0
Exp/Cntr=0.3,0.1

Type RM Length L Ch R = 1 ,26825   ,468,468,468
BEGIN DESCRIPTION:
Stream0009 55.0
END DESCRIPTION:
XS GIS Cut Line= 3
      1951824.97     13933974.97        1951675.       13933825.
      1951524.98     13933724.99
#Sta/Elev= 30
  4787.9 1956.92  4803.8  1956.6  4818.7 1955.03  4827.6 1953.78  4836.1 1951.68
  4859.9 1941.74  4871.7 1938.56  4897.1  1929.5  4902.3 1928.23  4918.5 1921.56
  4923.7 1918.75  4931.2 1916.18  4941.7 1910.53  4975.6 1897.81  4992.6 1895.66
  5000.2 1895.46  5000.5 1894.96    5004 1894.96  5004.2 1895.46  5010.9 1896.72
  5019.5 1899.49  5038.9  1903.3  5047.7 1906.36  5064.1 1910.23  5089.3 1918.51
  5103.8 1921.82  5116.9 1925.74  5136.2 1929.89  5154.2 1932.38  5180.3 1937.74
#Mann= 4 ,-1 , 0
  4787.9    .035       0  4818.7      .1       0  5000.2     .05       0
  5004.2      .1       0
Bank Sta=5000.2,5004.2
XS Rating Curve= 0 ,0
Exp/Cntr=0.3,0.1

Type RM Length L Ch R = 1 ,26357   ,452,452,452
BEGIN DESCRIPTION:
Stream0009 54.0
END DESCRIPTION:
XS GIS Cut Line= 3
      1952025.01     13933525.01        1951975.       13933475.
      1951675.03     13933325.02
#Sta/Elev= 30
  4925.4 1904.68    4957  1899.4  4968.9  1896.2  4973.6 1895.93  4990.5 1892.11
    4997  1889.3  5002.1 1886.08  5008.1 1884.15  5008.4 1883.49  5008.6 1882.99
  5012.1 1882.99  5012.4 1883.49  5032.3 1887.63  5049.1 1889.13    5064 1892.51
  5075.9 1894.27  5095.3 1898.91    5111 1904.22  5133.4 1909.87  5156.4 1918.06
  5194.6 1929.19  5206.7 1931.54  5220.1 1935.39  5240.7 1938.45  5261.7 1944.14
  5268.4 1945.28  5280.5 1948.66  5297.3 1954.98  5316.7 1957.27  5331.5 1957.98
#Mann= 3 ,-1 , 0
  4925.4      .1       0  5008.4     .05       0  5012.4      .1       0
Bank Sta=5008.4,5012.4
XS Rating Curve= 0 ,0
Exp/Cntr=0.3,0.1

Type RM Length L Ch R = 1 ,25905   ,433,433,433
BEGIN DESCRIPTION:
Stream0009 53.0
END DESCRIPTION:
XS GIS Cut Line= 3
        1952275.       13933225.        1952125.       13933075.
      1951875.03       13933075.
#Sta/Elev= 30
  4783.6 1931.05  4828.2 1921.99  4844.1 1917.31  4866.4 1908.97  4922.7 1894.05
  4940.7 1890.42  4944.9    1889  4983.1 1883.59  4993.7 1881.25  5001.1 1878.54
  5013.1 1877.54  5023.1 1875.31  5023.3 1874.81  5027.1 1875.31  5040.1 1878.86
  5049.8 1884.26  5055.1 1886.27  5071.1 1890.38  5082.1 1893.42  5100.1 1895.25
  5103.1 1896.68  5115.1 1898.55  5127.1 1901.03  5133.1 1903.18  5156.3 1907.47
  5175.1 1911.88  5193.8 1918.15  5214.1 1922.96  5217.1 1924.23  5245.7 1929.08
#Mann= 4 ,-1 , 0
  4783.6      .1       0  5023.1     .05       0  5027.1      .1       0
  5071.1     .07       0
Bank Sta=5023.1,5027.1
XS Rating Curve= 0 ,0
Exp/Cntr=0.3,0.1

Type RM Length L Ch R = 1 ,25472   ,431,431,431
BEGIN DESCRIPTION:
Stream0009 52.0
END DESCRIPTION:
XS GIS Cut Line= 3
      1952175.05     13932624.98        1952025.       13932675.
      1951775.02     13932774.99
#Sta/Elev= 30
  4846.4 1920.34  4895.3 1903.41  4936.4 1891.91  4952.2 1885.44  4964.8 1877.21
  4967.9 1875.55  4977.9 1868.72  4978.7 1866.87  4978.9 1866.37  4982.4 1866.37
  4982.7 1866.87  4990.2 1867.74  4999.7 1867.62  5002.8 1868.61  5015.7 1874.53
  5022.2 1876.47  5035.1 1877.56  5041.5 1878.64  5061.2 1878.91  5083.6 1880.55
  5099.7  1883.4  5112.6 1887.45  5138.5 1897.35  5170.8 1907.92  5190.2 1916.51
  5209.6 1923.62    5229 1927.91  5245.8 1930.97    5258 1934.28  5273.8 1936.38
#Mann= 4 ,-1 , 0
  4846.4      .1       0  4964.8     .07       0  4978.7     .05       0
  4982.7     .07       0
Bank Sta=4978.7,4982.7
XS Rating Curve= 0 ,0
Exp/Cntr=0.3,0.1

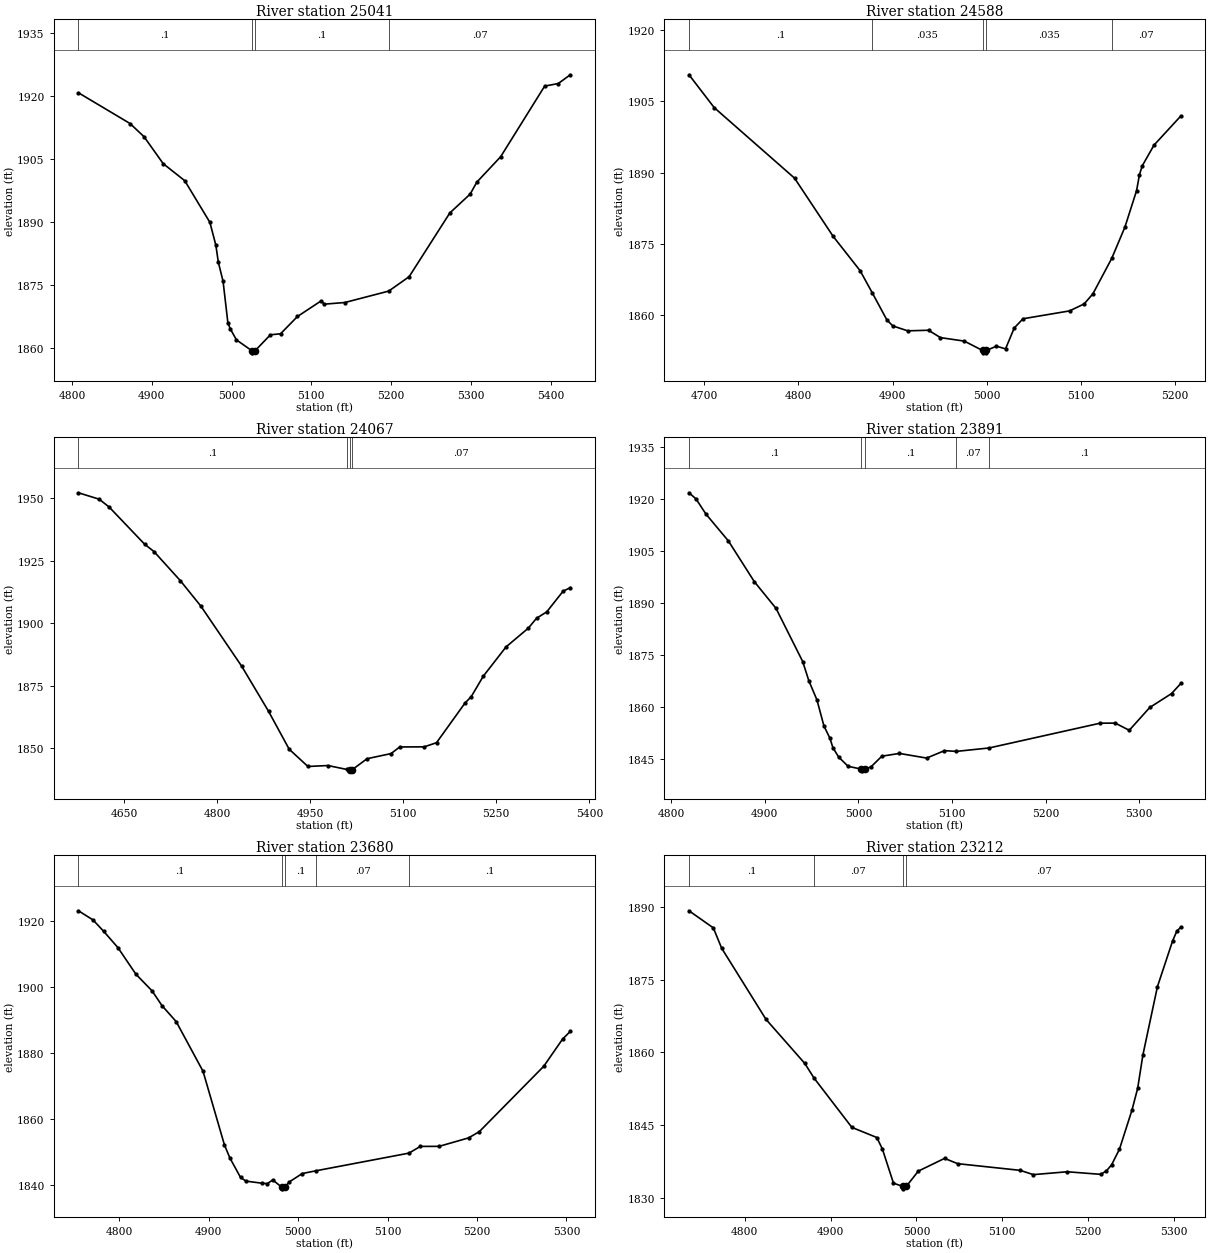
Type RM Length L Ch R = 1 ,25041   ,453,453,453
BEGIN DESCRIPTION:
Stream0009 51.0
END DESCRIPTION:
XS GIS Cut Line= 3
       1952216.9      13932272.9        1952025.       13932275.
      1951724.98     13932575.02
#Sta/Elev= 30
  4808.2 1920.87  4872.8 1913.55  4890.4  1910.4  4914.4 1903.98  4941.4 1899.92
  4972.9 1889.99  4980.4 1884.51  4983.4 1880.56  4989.4 1875.95  4995.4  1866.1
  4998.4 1864.62  5006.2 1861.99  5025.5 1859.41  5025.7 1858.91  5029.5 1859.41
  5048.7 1863.21  5061.4 1863.45  5082.6 1867.57  5112.2 1871.28  5116.4 1870.51
  5141.9  1870.9  5196.9 1873.62  5222.5 1877.05  5273.5 1892.24    5299 1896.74
  5307.3 1899.58  5337.2 1905.64  5392.3 1922.46  5409.3 1923.07  5424.4 1925.16
#Mann= 4 ,-1 , 0
  4808.2      .1       0  5025.5     .05       0  5029.5      .1       0
  5196.9     .07       0
Bank Sta=5025.5,5029.5
XS Rating Curve= 0 ,0
Exp/Cntr=0.3,0.1

Type RM Length L Ch R = 1 ,24588   ,521,521,521
BEGIN DESCRIPTION:
Stream0009 50.0
END DESCRIPTION:
XS GIS Cut Line= 3
      1952175.04     13931774.99        1951875.       13931875.
      1951675.03     13931924.99
#Sta/Elev= 30
  4683.7 1910.58  4710.5 1903.67  4795.8 1888.84  4836.9 1876.57  4865.4 1869.39
  4878.3 1864.74  4893.9 1859.01  4900.2 1857.75    4916 1856.72  4938.1 1856.84
  4950.8 1855.29  4976.1 1854.56  4995.5 1852.59  4995.8 1852.09  4999.3 1852.09
  4999.5 1852.59  5010.3 1853.49  5019.9 1852.92  5029.2 1857.33  5038.5 1859.26
  5087.9 1860.91  5103.4 1862.38  5112.7  1864.5  5132.7 1871.95  5146.7 1878.53
  5159.1 1886.21  5162.2  1889.6  5165.2 1891.45  5177.6 1895.78  5206.1 1901.91
#Mann= 5 ,-1 , 0
  4683.7      .1       0  4878.3    .035       0  4995.5    .035       0
  4999.5    .035       0  5132.7     .07       0
Bank Sta=4995.5,4999.5
XS Rating Curve= 0 ,0
Exp/Cntr=0.3,0.1

Type RM Length L Ch R = 1 ,24067   ,176,176,176
BEGIN DESCRIPTION:
Stream0009 49.0
END DESCRIPTION:
XS GIS Cut Line= 3
      1952333.39     13931491.03      1951891.48     13931432.55
      1951575.02     13931574.99
#Sta/Elev= 30
  4576.5 1952.11  4609.9 1949.55    4626 1946.42  4683.1 1931.59  4698.3 1928.63
  4740.9 1916.97  4773.9 1906.83  4839.8 1882.78  4882.9 1864.86  4916.2  1849.7
  4946.4 1842.81  4978.7 1843.19    5009 1841.63    5014 1841.57  5014.3 1841.07
    5018 1841.57  5041.8 1845.92  5080.4 1847.96  5094.4 1850.61  5133.9 1850.65
  5153.7 1852.31  5199.7 1868.18  5209.6 1870.68  5229.1 1878.88  5265.8 1890.57
  5301.7 1898.06  5314.9    1902  5331.3 1904.54  5357.6 1912.77  5369.3 1914.24
#Mann= 4 ,-1 , 0
  4576.5      .1       0    5009     .07       0    5014     .05       0
    5018     .07       0
Bank Sta=5014,5018
XS Rating Curve= 0 ,0
Exp/Cntr=0.3,0.1

Type RM Length L Ch R = 1 ,23891   ,211,211,211
BEGIN DESCRIPTION:
Mapping XS 1acdbf93
END DESCRIPTION:
XS GIS Cut Line= 2
       1952175.5     13931360.18      1951687.45     13931165.36
#Sta/Elev= 30
    4819 1921.86  4826.5 1920.09  4837.1 1915.71  4861.2  1907.9  4888.8 1896.17
    4912 1888.44  4940.5 1873.08    4947 1867.57  4955.8 1861.92  4963.1 1854.52
  4969.6 1850.88  4972.8 1848.16  4978.9 1845.47    4989 1842.79  5003.1 1841.98
  5003.4 1841.48  5007.1 1841.98  5013.5 1842.64  5025.1 1845.72  5043.9 1846.51
  5072.9 1845.17    5092 1847.32  5104.6  1847.1  5139.6 1848.09  5258.2 1855.25
  5274.4 1855.28  5289.4  1853.2  5311.3 1859.79  5334.6 1863.82  5344.5 1866.74
#Mann= 5 ,-1 , 0
    4819      .1       0  5003.1     .05       0  5007.1      .1       0
  5104.6     .07       0  5139.6      .1       0
Bank Sta=5003.1,5007.1
XS Rating Curve= 0 ,0
Exp/Cntr=0.3,0.1

Type RM Length L Ch R = 1 ,23680   ,468,468,468
BEGIN DESCRIPTION:
Stream0009 48.0
END DESCRIPTION:
XS GIS Cut Line= 3
      1952174.97       13931125.        1951925.       13931125.
      1951624.97       13931125.
#Sta/Elev= 30
  4754.3 1922.95  4770.6 1920.18  4782.6 1916.72  4798.4 1911.82  4818.6 1903.75
  4836.6 1898.74  4847.8 1894.24  4863.6 1889.43  4893.6 1874.42  4917.6  1852.1
  4923.6 1848.21  4935.6 1842.28  4941.6 1841.19  4959.6 1840.55  4965.6 1840.43
  4971.6 1841.55  4981.6 1839.35  4981.9 1838.85  4985.6 1839.35  4989.6 1840.86
  5004.6 1843.48  5020.1 1844.32  5123.9 1849.65  5136.6 1851.68  5157.6  1851.7
  5190.6 1854.26  5202.6 1856.15  5274.6 1875.91  5295.6 1884.11  5304.3 1886.47
#Mann= 5 ,-1 , 0
  4754.3      .1       0  4981.6     .05       0  4985.6      .1       0
  5020.1     .07       0  5123.9      .1       0
Bank Sta=4981.6,4985.6
XS Rating Curve= 0 ,0
Exp/Cntr=0.3,0.1

Type RM Length L Ch R = 1 ,23212   ,595,595,595
BEGIN DESCRIPTION:
Stream0009 47.0
END DESCRIPTION:
XS GIS Cut Line= 3
      1952125.02     13930574.99        1951875.       13930675.
      1951575.02       13930725.
#Sta/Elev= 30
  4734.9 1889.17  4763.3 1885.64    4773 1881.45  4824.7 1866.78  4869.9  1857.7
  4880.6  1854.7  4924.8 1844.51  4953.9 1842.42  4960.4 1840.04  4973.3 1833.01
  4984.2 1832.34  4984.5 1831.84  4988.2 1832.34  5002.3  1835.5  5032.9 1838.12
  5048.1 1837.03  5121.1 1835.65  5136.3 1834.77  5175.9 1835.36  5214.8 1834.83
  5221.5 1835.53  5227.6 1836.79  5236.7 1839.99  5251.3 1848.04    5258 1852.58
  5264.1 1859.46    5281 1873.51  5298.7 1882.95  5303.6 1884.96  5308.3 1885.79
#Mann= 4 ,-1 , 0
  4734.9      .1       0  4880.6     .07       0  4984.2     .05       0
  4988.2     .07       0
Bank Sta=4984.2,4988.2
XS Rating Curve= 0 ,0
Exp/Cntr=0.3,0.1

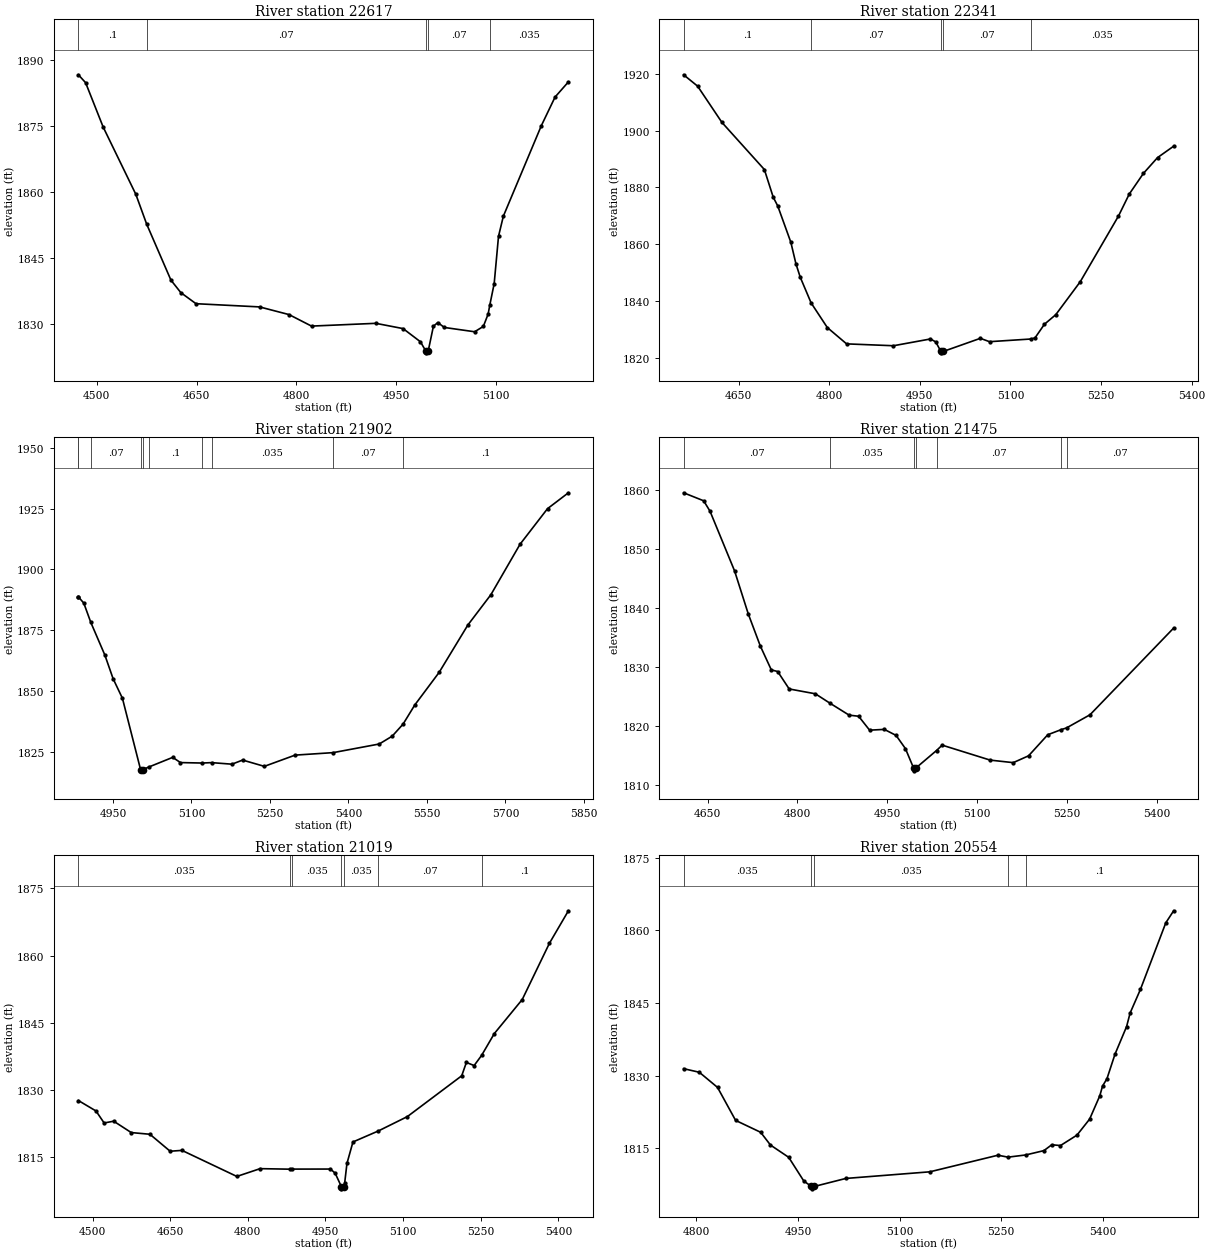
Type RM Length L Ch R = 1 ,22617   ,276,276,276
BEGIN DESCRIPTION:
Stream0009 45.1
END DESCRIPTION:
XS GIS Cut Line= 3
       1952101.3      13930533.6      1951715.88     13930239.32
      1951616.93     13930007.58
#Sta/Elev= 30
  4472.2 1886.64  4483.1 1884.84  4509.5 1874.74  4558.6 1859.43  4574.9 1852.64
  4611.4 1839.88  4626.3 1837.03  4649.1 1834.51  4744.7 1833.78    4789 1832.03
  4822.8 1829.41  4919.5 1830.04  4960.5 1828.84  4986.6 1825.84  4994.3 1823.82
  4994.6 1823.32  4998.4 1823.82  5006.1 1829.38  5012.7 1830.22  5022.5  1829.1
  5068.1 1828.12  5081.2 1829.34  5088.4 1832.15  5090.8 1834.12  5097.5  1839.1
    5104 1849.86  5111.3 1854.45  5168.4 1875.05    5189 1881.56  5209.1 1885.02
#Mann= 5 ,-1 , 0
  4472.2      .1       0  4574.9     .07       0  4994.3     .05       0
  4998.4     .07       0  5090.8    .035       0
Bank Sta=4994.3,4998.4
XS Rating Curve= 0 ,0
Exp/Cntr=0.3,0.1

Type RM Length L Ch R = 1 ,22341   ,439,439,439
BEGIN DESCRIPTION:
Stream0009 45.0
END DESCRIPTION:
XS GIS Cut Line= 3
        1952325.       13930275.        1951925.       13930075.
      1951575.02     13929975.01
#Sta/Elev= 30
  4558.9 1919.65  4582.1 1915.64  4622.3 1902.88  4692.6 1886.27  4707.3  1876.5
  4714.7 1873.45  4736.4 1860.66  4744.9 1853.02    4752 1848.33    4770 1839.27
  4796.8  1830.6  4828.7 1824.85  4906.3 1824.19  4967.6 1826.58  4976.3 1825.53
  4984.8 1822.19    4985 1821.69  4988.9 1822.19  5050.1  1826.8  5065.3 1825.62
  5133.5 1826.56  5140.5 1826.92  5156.2 1831.76    5175 1835.14  5215.5 1846.74
  5278.8 1869.89  5296.6 1877.62  5320.1 1884.92  5343.4 1890.46  5370.1 1894.49
#Mann= 5 ,-1 , 0
  4558.9      .1       0    4770     .07       0  4984.8     .05       0
  4988.9     .07       0  5133.5    .035       0
Bank Sta=4984.8,4988.9
XS Rating Curve= 0 ,0
Exp/Cntr=0.3,0.1

Type RM Length L Ch R = 1 ,21902   ,427,427,427
BEGIN DESCRIPTION:
Stream0009 44.0
END DESCRIPTION:
XS GIS Cut Line= 3
      1952374.97     13929874.99        1952275.       13929825.
      1951474.99       13929625.
#Sta/Elev= 30
  4883.9  1888.8  4884.1 1888.73  4894.3  1886.2  4907.7 1878.28  4934.6 1864.85
  4950.3 1855.18  4968.1 1847.15  5002.8 1817.87    5003 1817.37  5006.9 1817.87
  5019.8 1819.05  5064.2  1822.9    5079 1820.76  5120.6 1820.57  5138.5 1820.74
  5177.4  1820.1  5197.8 1821.79  5239.3 1819.21    5298 1823.82  5370.7 1824.84
  5458.8 1828.38  5483.6  1831.6  5504.4 1836.55  5526.8 1844.41  5573.3 1857.78
  5628.2 1877.22  5672.2 1889.66  5727.9 1910.36  5780.4 1924.96  5820.3 1931.48
#Mann= 10 ,-1 , 0
  4883.9     .07       0  4884.1      .1       0  4907.7     .07       0
  5002.8     .05       0  5006.9     .07       0  5019.8      .1       0
  5120.6     .07       0  5138.5    .035       0  5370.7     .07       0
  5504.4      .1       0
Bank Sta=5002.8,5006.9
XS Rating Curve= 0 ,0
Exp/Cntr=0.3,0.1

Type RM Length L Ch R = 1 ,21475   ,456,456,456
BEGIN DESCRIPTION:
Stream0009 43.0
END DESCRIPTION:
XS GIS Cut Line= 3
      1952575.04     13929675.03        1952275.       13929425.
      1951874.96     13929274.99
#Sta/Elev= 30
    4610 1859.53  4643.5 1858.17  4654.1  1856.4  4695.1 1846.27    4718 1838.96
  4738.1 1833.52  4756.4 1829.48    4767 1829.21  4786.2 1826.25  4829.9 1825.43
  4853.7 1823.87  4886.2 1821.81  4902.1 1821.62  4920.4 1819.26    4945 1819.39
  4964.6 1818.37  4980.2 1816.13  4993.7 1812.86    4994 1812.36  4997.9 1812.86
  5032.1 1815.81  5041.5 1816.72  5121.6 1814.18  5160.1 1813.75  5185.7 1814.91
  5217.7 1818.48  5239.8 1819.34    5249 1819.64  5288.2 1821.87  5427.8 1836.58
#Mann= 7 ,-1 , 0
    4610     .07       0  4853.7    .035       0  4993.7    .035       0
  4997.9    .035       0  5032.1     .07       0  5239.8    .035       0
    5249     .07       0
Bank Sta=4993.7,4997.9
XS Rating Curve= 0 ,0
Exp/Cntr=0.3,0.1

Type RM Length L Ch R = 1 ,21019   ,465,465,465
BEGIN DESCRIPTION:
Stream0009 42.0
END DESCRIPTION:
XS GIS Cut Line= 3
      1952525.04     13929375.03        1952125.       13929025.
      1951709.46     13929022.66
#Sta/Elev= 30
  4472.4 1827.62  4506.5 1825.28  4522.2  1822.6  4540.7    1823  4574.6 1820.46
  4610.7 1820.08  4649.8 1816.29  4672.6 1816.48  4778.7 1810.66  4823.7  1812.4
  4881.7 1812.28  4884.7  1812.3  4959.6 1812.31  4968.7 1811.39  4980.7 1808.39
  4980.9 1807.89  4984.9 1808.39  4987.1 1809.19  4991.5 1813.56  5003.1 1818.36
  5052.4 1820.83  5108.3 1824.03  5213.3 1833.14  5222.3 1836.12  5237.3 1835.43
  5251.7 1837.69  5276.3 1842.57  5330.3 1850.18  5382.9 1862.76  5419.5    1870
#Mann= 7 ,-1 , 0
  4472.4    .035       0  4881.7     .07       0  4884.7    .035       0
  4980.7    .035       0  4984.9    .035       0  5052.4     .07       0
  5251.7      .1       0
Bank Sta=4980.7,4984.9
XS Rating Curve= 0 ,0
Exp/Cntr=0.3,0.1

Type RM Length L Ch R = 1 ,20554   ,445,445,445
BEGIN DESCRIPTION:
Stream0009 41.0
END DESCRIPTION:
XS GIS Cut Line= 3
      1952625.02     13929225.04        1952525.       13929025.
      1952224.97     13928624.96
#Sta/Elev= 30
  4781.1 1831.42  4804.3 1830.68  4831.2 1827.55  4857.9 1820.73  4894.9 1818.27
  4909.4 1815.63  4936.3  1813.1  4958.6  1808.2  4969.8 1807.08  4970.1 1806.58
  4974.3 1807.08  5020.7 1808.73  5144.8  1810.1  5245.3 1813.53  5260.2 1813.13
  5286.2 1813.58  5313.2 1814.48  5324.8 1815.69  5337.7 1815.53    5362 1817.68
  5380.7 1820.99  5395.7  1825.8  5399.8 1827.82  5406.3 1829.34  5418.2 1834.42
  5435.3 1840.12  5440.5 1842.92  5455.7 1847.79  5493.2 1861.57  5504.8 1864.06
#Mann= 5 ,-1 , 0
  4781.1    .035       0  4969.8    .035       0  4974.3    .035       0
  5260.2     .07       0  5286.2      .1       0
Bank Sta=4969.8,4974.3
XS Rating Curve= 0 ,0
Exp/Cntr=0.3,0.1

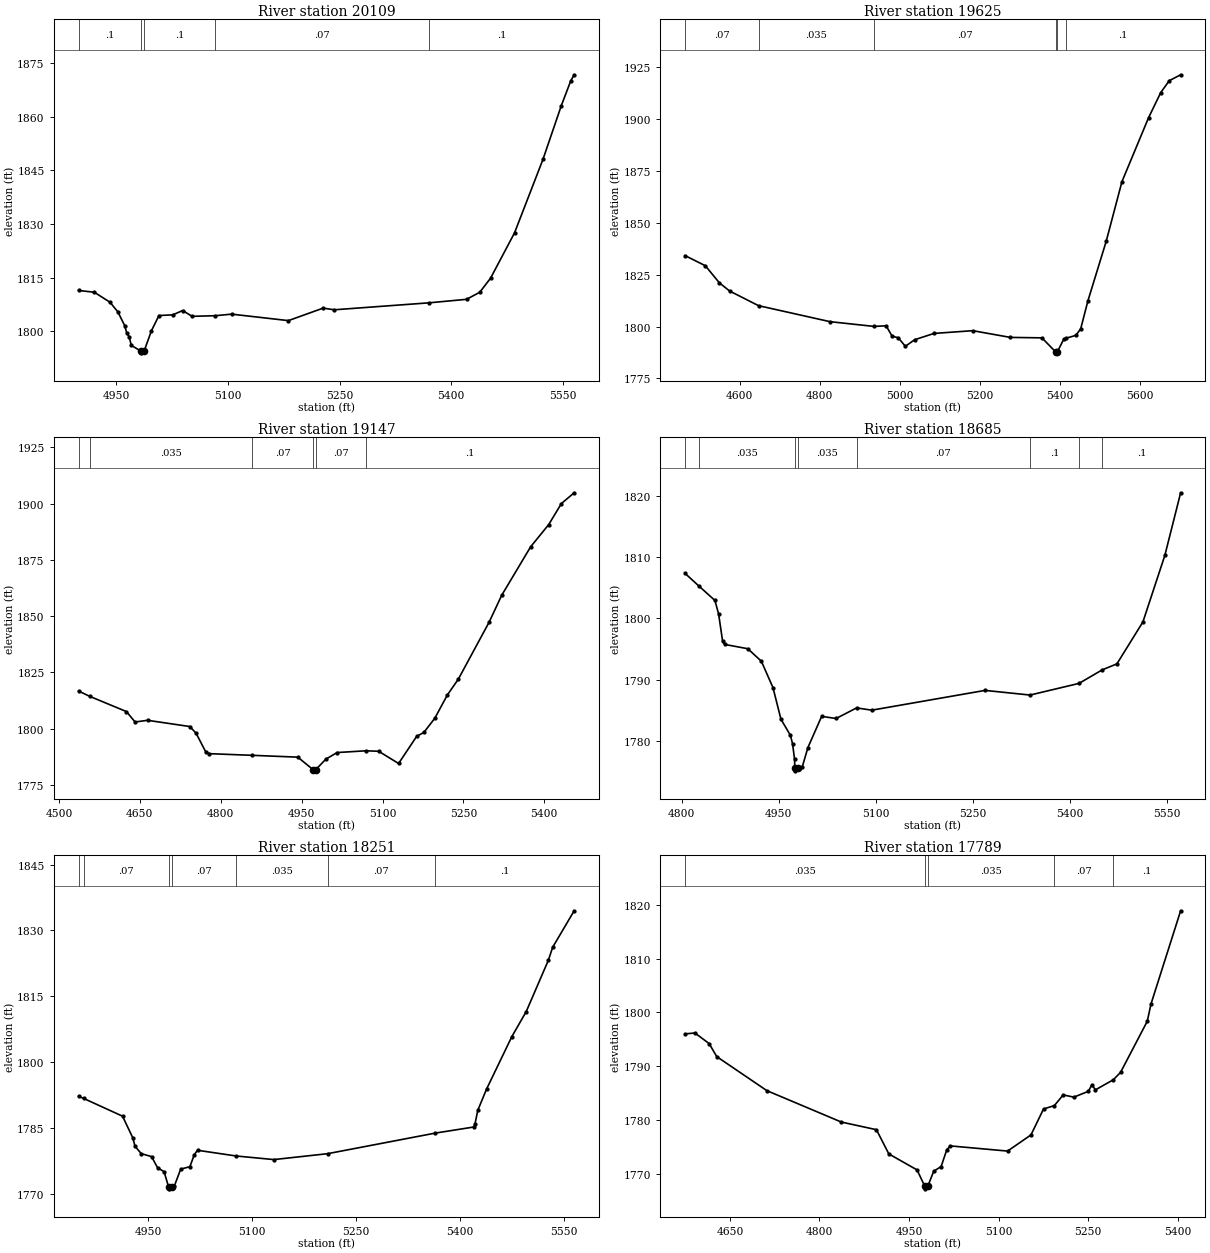
Type RM Length L Ch R = 1 ,20109   ,484,484,484
BEGIN DESCRIPTION:
Stream0009 40.0
END DESCRIPTION:
XS GIS Cut Line= 3
        1952925.     13928975.02        1952925.       13928875.
      1952525.01     13928475.01
#Sta/Elev= 30
  4899.4  1811.4  4920.5  1810.9  4941.5 1808.11  4952.2 1805.38  4961.2 1801.59
  4964.2 1799.42  4967.2 1798.46  4970.2 1796.03  4982.9 1794.44  4983.2 1793.94
  4987.4 1794.44  4997.2 1800.12  5007.3 1804.38    5026 1804.58  5039.1 1805.78
  5051.8 1804.16    5083 1804.33  5104.9 1804.77  5181.2 1802.96  5227.9 1806.46
  5242.7 1805.99  5370.2 1807.94  5420.5 1808.92  5438.3  1810.9  5452.8 1814.85
    5485 1827.53  5523.2  1848.1  5547.8 1863.12  5560.5 1870.07  5565.1 1871.77
#Mann= 5 ,-1 , 0
  4899.4      .1       0  4982.9     .05       0  4987.4      .1       0
    5083     .07       0  5370.2      .1       0
Bank Sta=4982.9,4987.4
XS Rating Curve= 0 ,0
Exp/Cntr=0.3,0.1

Type RM Length L Ch R = 1 ,19625   ,478,478,478
BEGIN DESCRIPTION:
Stream0009 39.0
END DESCRIPTION:
XS GIS Cut Line= 3
      1953724.99     13929174.98        1953375.       13928775.
        1953475.     13928074.99
#Sta/Elev= 30
  4463.8 1834.15  4514.4 1829.27  4549.6 1821.01  4575.1  1817.1  4647.3 1810.05
    4826 1802.34  4936.3 1800.05  4966.3 1800.36  4981.2 1795.35  4996.6 1794.61
  5014.3 1790.46  5037.5 1793.64    5086 1796.68  5182.9    1798  5276.9 1794.76
  5355.7 1794.55  5389.7 1787.83  5390.1 1787.33  5394.3 1787.83  5410.2 1793.86
  5415.5 1794.35  5440.5 1795.74  5452.6  1798.9  5470.8 1812.48  5516.3 1841.01
  5555.7 1869.77  5622.4 1900.64  5652.7 1912.67  5673.9 1918.38  5702.4 1921.23
#Mann= 6 ,-1 , 0
  4463.8     .07       0  4647.3    .035       0  4936.3     .07       0
  5389.7     .05       0  5394.3     .07       0  5415.5      .1       0
Bank Sta=5389.7,5394.3
XS Rating Curve= 0 ,0
Exp/Cntr=0.3,0.1

Type RM Length L Ch R = 1 ,19147   ,462,462,462
BEGIN DESCRIPTION:
Stream0009 38.0
END DESCRIPTION:
XS GIS Cut Line= 3
      1954024.99     13928974.99        1953775.       13928575.
        1953575.       13928175.
#Sta/Elev= 30
  4536.5 1816.75  4557.2 1814.38  4625.1 1807.64  4641.2    1803  4664.3 1803.76
  4742.7 1800.99  4754.4 1797.98  4772.1 1789.78  4779.1 1788.94  4858.3 1788.21
  4942.9  1787.4  4971.4 1781.82  4971.7 1781.32  4976.1 1781.82  4994.9  1786.5
  5015.8 1789.44  5069.2 1790.22  5092.9 1790.01  5129.8 1784.58  5163.3 1796.62
  5176.7 1798.38  5196.9 1804.65  5220.4 1815.06  5240.5    1822  5297.5 1847.24
    5321 1859.26  5374.6 1880.77  5408.2 1890.67  5431.7    1900  5455.4 1904.78
#Mann= 6 ,-1 , 0
  4536.5     .07       0  4557.2    .035       0  4858.3     .07       0
  4971.4     .05       0  4976.1     .07       0  5069.2      .1       0
Bank Sta=4971.4,4976.1
XS Rating Curve= 0 ,0
Exp/Cntr=0.3,0.1

Type RM Length L Ch R = 1 ,18685   ,434,434,434
BEGIN DESCRIPTION:
Stream0009 37.0
END DESCRIPTION:
XS GIS Cut Line= 3
        1954175.       13928875.        1954175.       13928675.
      1953774.99     13928274.99
#Sta/Elev= 30
  4805.1 1807.35  4826.8 1805.25  4851.2 1802.93  4856.9 1800.71  4862.9 1796.39
  4866.2 1795.75  4901.9 1795.05  4922.9 1793.01  4940.9 1788.69  4953.2 1783.53
  4967.9 1780.89  4971.2 1779.47  4974.2 1777.03  4974.7  1775.6  4975.1  1775.1
  4979.8  1775.6  4985.9 1775.66  4994.9 1778.91  5016.1    1784  5038.4 1783.65
  5070.1 1785.38  5093.6 1785.01  5268.6 1788.24  5338.1 1787.48  5413.7 1789.38
  5449.7  1791.6  5472.3 1792.57  5512.5 1799.42  5546.4 1810.29  5570.8 1820.52
#Mann= 8 ,-1 , 0
  4805.1      .1       0  4826.8    .035       0  4974.7    .035       0
  4979.8    .035       0  5070.1     .07       0  5338.1      .1       0
  5413.7     .07       0  5449.7      .1       0
Bank Sta=4974.7,4979.8
XS Rating Curve= 0 ,0
Exp/Cntr=0.3,0.1

Type RM Length L Ch R = 1 ,18251   ,462,462,462
BEGIN DESCRIPTION:
Stream0009 36.0
END DESCRIPTION:
XS GIS Cut Line= 3
      1954475.03       13928325.        1954325.       13928325.
      1953925.01     13927925.01
#Sta/Elev= 30
  4849.4 1792.25  4856.5 1791.76  4912.8 1787.71  4927.8 1782.72  4930.8 1780.87
  4939.8 1779.19  4954.8  1778.5  4963.5 1775.95  4972.8 1775.09  4979.2 1771.67
  4979.6 1771.17  4984.3 1771.67  4987.8 1771.88  4996.8 1775.65  5010.1 1776.22
  5016.5 1778.96  5021.1 1779.95  5076.9 1778.65  5131.4 1777.83  5208.9 1779.17
  5364.2 1783.85  5419.9 1785.24  5421.7 1785.82  5425.9 1789.05  5438.6 1793.89
  5475.1 1805.83  5495.9 1811.54  5527.7 1823.16  5534.1 1826.18  5565.1 1834.47
#Mann= 7 ,-1 , 0
  4849.4    .035       0  4856.5     .07       0  4979.2     .05       0
  4984.3     .07       0  5076.9    .035       0  5208.9     .07       0
  5364.2      .1       0
Bank Sta=4979.2,4984.3
XS Rating Curve= 0 ,0
Exp/Cntr=0.3,0.1

Type RM Length L Ch R = 1 ,17789   ,573,573,573
BEGIN DESCRIPTION:
Stream0009 35.0
END DESCRIPTION:
XS GIS Cut Line= 3
      1954624.97     13928224.96        1954375.       13927875.
      1953974.97       13927875.
#Sta/Elev= 30
  4574.9 1796.02  4591.4 1796.18  4615.1 1794.22    4628 1791.79  4711.9 1785.48
  4836.6 1779.65  4895.4 1778.23  4916.2 1773.73  4963.5 1770.76  4976.3 1767.75
  4976.7 1767.25  4981.5 1767.75  4991.4 1770.52  5003.8 1771.39  5013.3 1774.52
  5019.3 1775.22  5115.1 1774.26  5154.3 1777.26  5175.3 1782.07  5193.5 1782.71
  5208.3 1784.69  5226.1 1784.27  5250.3 1785.35  5256.3 1786.55  5262.3 1785.63
  5292.1 1787.49  5304.3 1788.86  5349.1 1798.36  5355.3 1801.55    5405 1818.87
#Mann= 5 ,-1 , 0
  4574.9    .035       0  4976.3    .035       0  4981.5    .035       0
  5193.5     .07       0  5292.1      .1       0
Bank Sta=4976.3,4981.5
XS Rating Curve= 0 ,0
Exp/Cntr=0.3,0.1

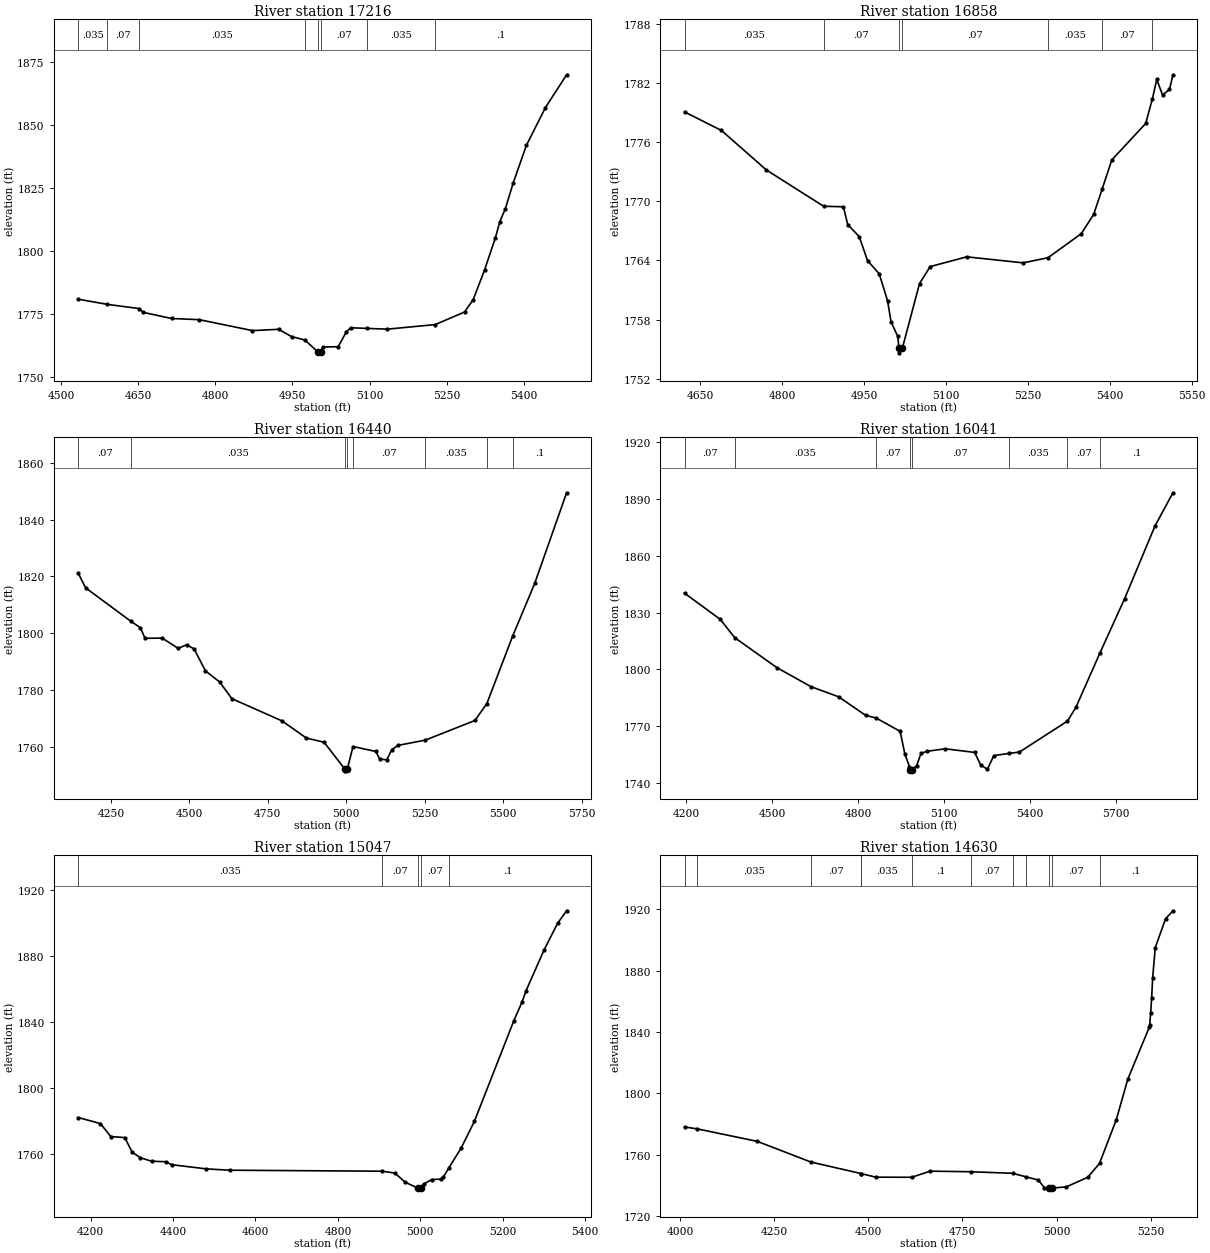
Type RM Length L Ch R = 1 ,17216   ,358,358,358
BEGIN DESCRIPTION:
Stream0009 34.0
END DESCRIPTION:
XS GIS Cut Line= 3
      1954875.06      13927919.2      1954731.98     13927474.18
      1954449.97     13927082.74
#Sta/Elev= 30
  4533.4 1780.98  4590.2 1778.93  4650.8  1777.3  4660.1 1775.75  4714.9 1773.34
  4768.7 1772.87  4872.3 1768.54  4923.1 1769.05  4948.3 1766.15  4974.1 1764.82
  4998.8 1760.22  4999.3 1759.72  5005.2 1760.22  5009.6 1762.03    5039 1762.15
  5054.8 1768.01  5063.4 1769.66  5094.9 1769.42  5134.3 1769.11  5227.7 1770.92
  5284.7  1775.9  5301.5 1780.76  5323.7 1792.56  5344.9 1805.42  5353.5 1811.77
  5364.3 1816.95  5379.2 1826.92  5405.1 1842.01    5442 1856.93  5483.3 1869.97
#Mann= 8 ,-1 , 0
  4533.4    .035       0  4590.2     .07       0  4650.8    .035       0
  4974.1     .07       0  4998.8     .05       0  5005.2     .07       0
  5094.9    .035       0  5227.7      .1       0
Bank Sta=4998.8,5005.2
XS Rating Curve= 0 ,0
Exp/Cntr=0.3,0.1

Type RM Length L Ch R = 1 ,16858   ,418,418,418
BEGIN DESCRIPTION:
Stream0009 33.0
END DESCRIPTION:
XS GIS Cut Line= 4
      1955013.89     13927893.86        1955075.       13927525.
      1955076.74     13927443.33        1954775.       13927125.
#Sta/Elev= 30
  4621.5 1779.07    4689 1777.19  4771.1 1773.19  4876.1  1769.5  4912.3 1769.45
  4920.2 1767.65  4941.4 1766.41  4956.6 1763.97  4977.9 1762.65  4993.1 1759.92
  4999.6 1757.78  5011.9 1756.29    5014 1755.13  5014.5 1754.63  5020.4 1755.13
  5051.7 1761.66  5071.2 1763.38    5138 1764.37  5241.5 1763.76    5287 1764.28
  5348.1 1766.73  5370.7 1768.69  5386.2 1771.26  5403.8  1774.2  5465.8  1777.9
  5478.1  1780.4  5486.1 1782.37  5496.7 1780.79  5509.4 1781.35  5515.7 1782.84
#Mann= 7 ,-1 , 0
  4621.5    .035       0  4876.1     .07       0    5014     .05       0
  5020.4     .07       0    5287    .035       0  5386.2     .07       0
  5478.1      .1       0
Bank Sta=5014,5020.4
XS Rating Curve= 0 ,0
Exp/Cntr=0.3,0.1

Type RM Length L Ch R = 1 ,16440   ,399,399,399
BEGIN DESCRIPTION:
Stream0009 32.2
END DESCRIPTION:
XS GIS Cut Line= 3
      1955483.59     13928474.79      1955441.93     13927672.66
      1955720.52     13926973.97
#Sta/Elev= 30
  4146.2  1821.1  4169.8 1815.99    4313 1804.31    4344 1801.99    4359 1798.26
  4413.1 1798.36  4464.2 1794.76  4491.2 1795.97  4515.1 1794.54  4551.3 1786.82
  4596.4 1782.94  4635.4 1777.06  4794.9 1769.26  4872.7 1763.23  4929.1 1761.75
  4996.1  1752.2  4996.6  1751.7  5002.7  1752.2  5021.4 1760.24  5093.9 1758.51
    5106  1755.9  5128.6 1755.54  5144.7  1759.1  5164.7 1760.65  5251.2 1762.48
  5409.6 1769.39  5447.6 1775.32  5529.6 1799.01  5600.1 1817.58  5701.6 1849.41
#Mann= 8 ,-1 , 0
  4146.2     .07       0    4313    .035       0  4996.1    .035       0
  5002.7    .035       0  5021.4     .07       0  5251.2    .035       0
  5447.6     .07       0  5529.6      .1       0
Bank Sta=4996.1,5002.7
XS Rating Curve= 0 ,0
Exp/Cntr=0.3,0.1

Type RM Length L Ch R = 1 ,16041   ,994,994,994
BEGIN DESCRIPTION:
Stream0009 32.1
END DESCRIPTION:
XS GIS Cut Line= 4
      1955903.58     13928574.31      1955784.73     13927598.44
      1955768.43     13927381.63      1955889.98      13926892.4
#Sta/Elev= 30
    4195 1840.16  4319.8 1826.36  4369.9 1816.76  4517.5 1800.92  4636.3  1790.9
    4733 1785.57  4826.7 1775.83  4863.8 1774.38  4947.5 1767.36  4963.7 1755.53
  4979.9 1748.83  4980.5 1747.06    4981 1746.56  4987.2 1747.06    5005 1749.27
  5020.3 1755.76  5041.3 1756.86  5104.8 1758.18  5207.3 1756.27  5228.4  1749.7
    5252 1747.36  5274.4 1754.58  5326.5 1755.72  5363.9 1756.46  5531.5 1772.77
  5560.8 1779.97  5645.3 1808.82  5730.8 1837.23  5836.8 1875.55  5899.6  1893.1
#Mann= 8 ,-1 , 0
    4195     .07       0  4369.9    .035       0  4863.8     .07       0
  4980.5     .05       0  4987.2     .07       0  5326.5    .035       0
  5531.5     .07       0  5645.3      .1       0
Bank Sta=4980.5,4987.2
XS Rating Curve= 0 ,0
Exp/Cntr=0.3,0.1

Type RM Length L Ch R = 1 ,15047   ,417,417,417
BEGIN DESCRIPTION:
Stream0009 32.0
END DESCRIPTION:
XS GIS Cut Line= 3
        1956425.     13927924.99        1956225.       13927125.
      1956024.98     13926824.97
#Sta/Elev= 30
  4169.9 1782.29  4223.6 1778.62    4249 1770.78    4283 1770.16  4300.3 1761.46
  4320.1    1758    4348 1755.87  4381.9 1755.56  4396.8 1753.77  4480.9 1751.24
  4537.8 1750.44  4906.9 1749.84  4938.2 1748.72  4963.3 1743.19  4993.3 1739.68
  4993.8 1739.18  5000.6 1739.68  5008.3 1742.09  5027.8  1744.8  5049.4 1745.04
  5055.9 1746.28  5068.6 1751.57  5098.8 1763.67  5131.2 1779.92  5226.8 1840.65
  5246.6 1851.91  5256.5 1858.81  5300.7 1883.72  5333.2 1899.65  5355.1 1907.25
#Mann= 5 ,-1 , 0
  4169.9    .035       0  4906.9     .07       0  4993.3     .05       0
  5000.6     .07       0  5068.6      .1       0
Bank Sta=4993.3,5000.6
XS Rating Curve= 0 ,0
Exp/Cntr=0.3,0.1

Type RM Length L Ch R = 1 ,14630   ,463,463,463
BEGIN DESCRIPTION:
Stream0009 31.0
END DESCRIPTION:
XS GIS Cut Line= 3
      1957174.97     13927624.97        1956525.       13926875.
      1956474.99     13926574.96
#Sta/Elev= 30
  4012.2    1778  4044.6 1776.83  4205.1 1768.63  4347.7 1755.12  4481.5 1747.58
  4481.8 1747.56  4519.8 1745.26  4615.3  1745.2  4664.4 1749.19  4772.2  1748.8
  4882.9  1747.8  4917.4 1745.59  4951.4 1743.39  4967.3 1738.44  4979.8 1738.15
  4980.3 1737.65  4987.1 1738.15  5025.6 1738.92  5082.9 1745.22  5113.9 1754.26
  5158.5 1782.77  5188.9 1809.14    5246 1843.05  5247.2 1844.71  5249.8 1852.67
  5252.4 1862.39    5255 1875.28  5261.9 1895.06  5289.3 1913.84  5308.8 1919.05
#Mann= 12 ,-1 , 0
  4012.2     .07       0  4044.6    .035       0  4347.7     .07       0
  4481.5      .1       0  4481.8    .035       0  4615.3      .1       0
  4772.2     .07       0  4882.9      .1       0  4917.4     .07       0
  4979.8     .05       0  4987.1     .07       0  5113.9      .1       0
Bank Sta=4979.8,4987.1
XS Rating Curve= 0 ,0
Exp/Cntr=0.3,0.1