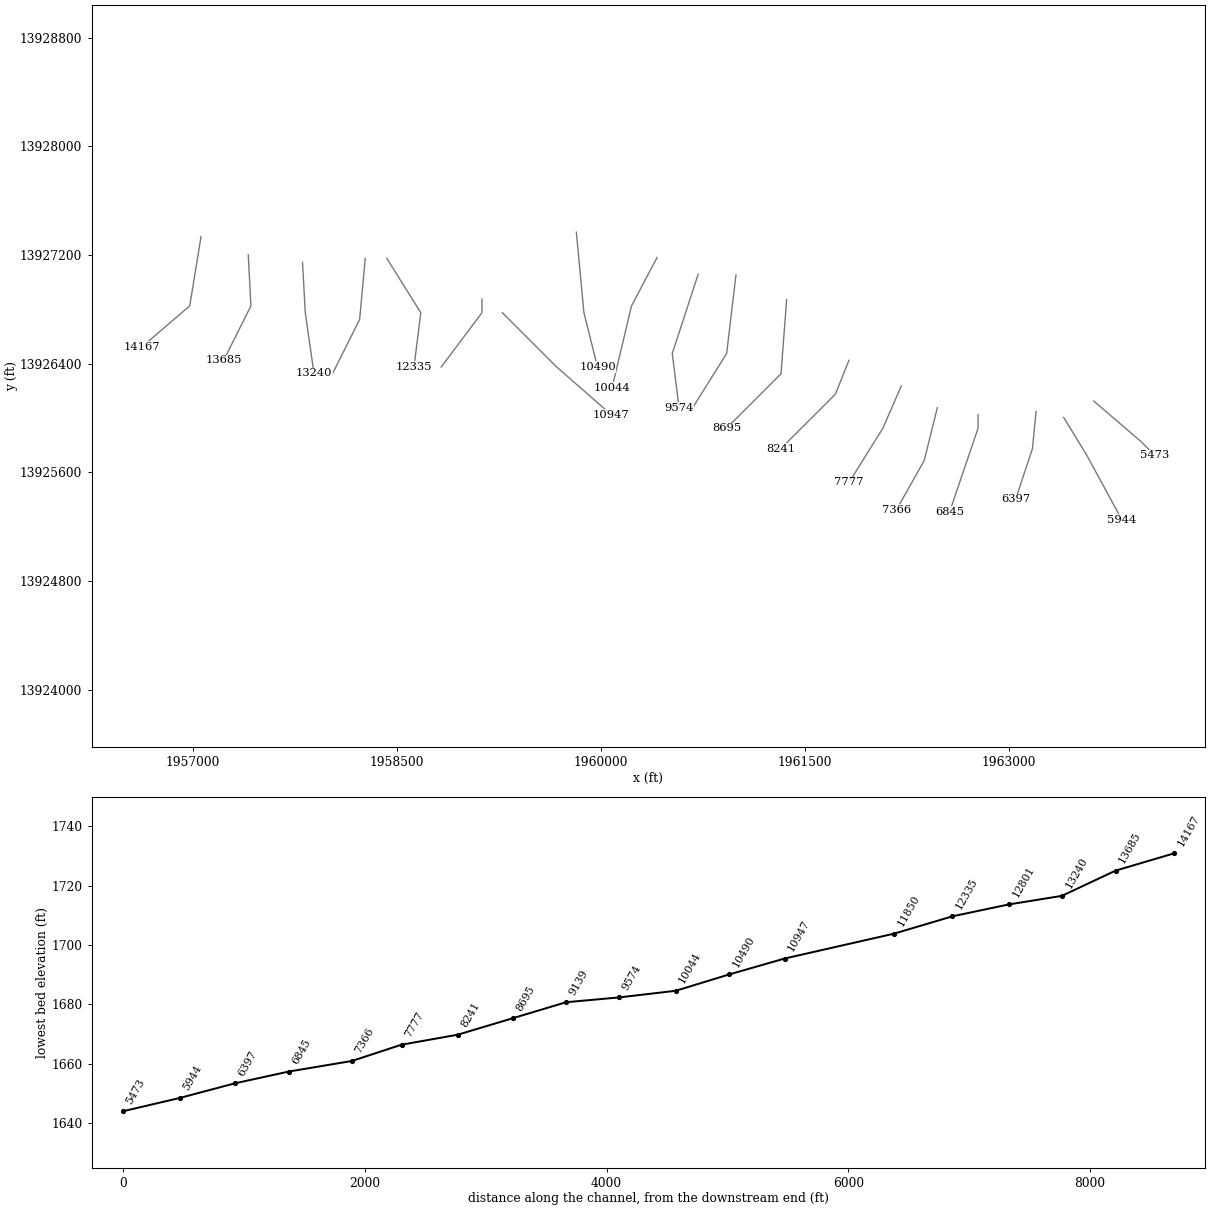
HEC-RAS study Stream0009.prj: Stream0009 Base Level Engineering

--- Stream0009.g01 (geometry) --- (continued)

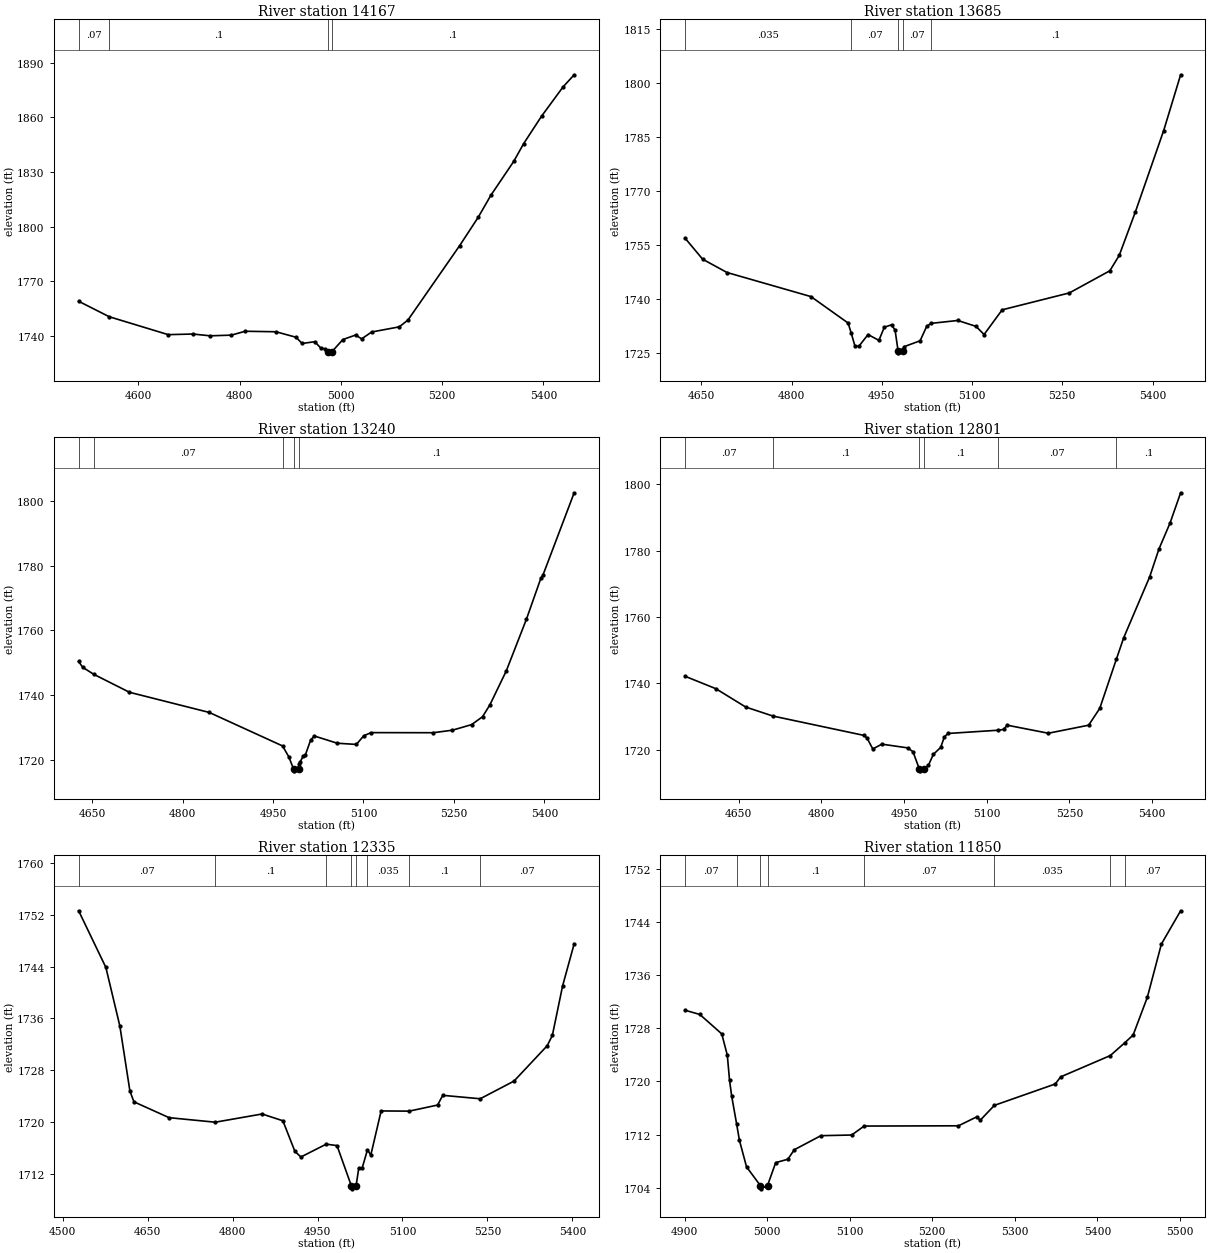
Type RM Length L Ch R = 1 ,14167   ,482,482,482
BEGIN DESCRIPTION:
Stream0009 30.0
END DESCRIPTION:
XS GIS Cut Line= 3
      1957058.24     13927335.83        1956975.       13926825.
      1956625.04     13926525.03
#Sta/Elev= 30
  4482.3 1759.13  4542.9 1750.63  4659.2 1740.82  4707.8 1741.16  4742.1 1740.18
  4783.8 1740.55  4811.2 1742.68    4872  1742.4  4911.5  1739.4  4923.6 1735.98
  4948.6 1736.94  4960.1 1733.57  4969.2 1732.96  4974.7 1731.34  4975.2 1730.84
    4982 1731.34  5004.1 1738.13  5029.3 1740.62  5041.1  1738.5  5060.9 1742.27
  5115.5  1745.1  5132.6 1748.84  5234.6 1789.62  5271.5 1805.29  5296.4 1817.32
  5341.4 1835.84  5361.2 1845.68  5396.4 1860.66  5438.9 1876.74  5460.8 1883.38
#Mann= 4 ,-1 , 0
  4482.3     .07       0  4542.9      .1       0  4974.7     .05       0
    4982      .1       0
Bank Sta=4974.7,4982
XS Rating Curve= 0 ,0
Exp/Cntr=0.3,0.1

Type RM Length L Ch R = 1 ,13685   ,445,445,445
BEGIN DESCRIPTION:
Stream0009 29.0
END DESCRIPTION:
XS GIS Cut Line= 3
      1957405.66     13927200.88        1957425.       13926825.
        1957225.     13926424.99
#Sta/Elev= 30
  4623.1 1756.89  4652.3 1751.05  4692.8 1747.36  4832.3 1740.67  4894.1 1733.32
  4898.9 1730.69  4905.6 1726.83  4912.1 1726.92  4927.2 1730.13  4945.2 1728.51
  4954.2 1732.17  4966.2 1732.83  4972.1 1731.37  4977.1 1725.55  4977.6 1725.05
  4985.4 1725.55  4987.2 1726.77  5013.7  1728.4  5024.9 1732.49  5032.2 1733.24
  5076.3 1734.04  5106.6  1732.4    5120 1730.14  5150.1    1737  5261.9  1741.7
    5329 1747.84  5344.6  1752.1  5371.4 1764.16  5418.5 1786.78  5446.7 1802.28
#Mann= 5 ,-1 , 0
  4623.1    .035       0  4898.9     .07       0  4977.1     .05       0
  4985.4     .07       0  5032.2      .1       0
Bank Sta=4977.1,4985.4
XS Rating Curve= 0 ,0
Exp/Cntr=0.3,0.1

Type RM Length L Ch R = 1 ,13240   ,439,439,439
BEGIN DESCRIPTION:
Stream0009 28.0
END DESCRIPTION:
XS GIS Cut Line= 3
      1957804.72     13927146.44        1957825.       13926775.
      1957888.83     13926329.74
#Sta/Elev= 30
  4627.6 1750.39  4634.2 1748.59  4652.6 1746.42  4711.9 1740.85  4844.1 1734.62
  4965.8 1724.25  4976.3 1720.83  4984.1 1717.05  4984.6 1716.55  4992.5 1717.05
  4993.4 1718.67  4994.4 1719.13  5000.4 1721.23  5003.3  1721.3  5012.5 1726.14
  5018.6 1727.32  5056.5 1725.09  5088.2 1724.72  5100.4 1727.39  5112.5 1728.37
  5215.5 1728.34  5247.4 1729.12  5279.2 1730.84  5297.4 1733.28  5309.5 1736.91
  5336.8 1747.46  5370.1 1763.39  5394.4 1776.24  5397.4 1776.98  5449.4 1802.56
#Mann= 5 ,-1 , 0
  4627.6    .035       0  4652.6     .07       0  4965.8      .1       0
  4984.1     .05       0  4992.5      .1       0
Bank Sta=4984.1,4992.5
XS Rating Curve= 0 ,0
Exp/Cntr=0.3,0.1

Type RM Length L Ch R = 1 ,12801   ,466,466,466
BEGIN DESCRIPTION:
Stream0009 27.0
END DESCRIPTION:
XS GIS Cut Line= 3
      1958266.23     13927174.67        1958225.       13926725.
      1958024.99     13926324.97
#Sta/Elev= 30
    4553 1742.14  4608.7 1738.41  4662.9 1732.88  4712.4 1730.16  4876.8 1724.36
  4882.8  1723.6  4893.4 1720.26  4909.9  1721.7  4956.8 1720.58  4966.3 1719.43
    4978 1714.17  4978.5 1713.67  4986.5 1714.17  4994.3 1715.35  5003.3 1718.63
  5016.6 1720.73  5023.3 1723.92    5030 1724.92  5120.2 1725.89  5130.6 1726.13
  5137.3 1727.41  5211.8 1724.99  5284.9 1727.41  5305.1 1732.47  5335.3 1747.32
  5348.7 1753.81  5395.6 1772.05  5412.4 1780.43  5432.5 1788.24  5451.8 1797.38
#Mann= 6 ,-1 , 0
    4553     .07       0  4712.4      .1       0    4978     .05       0
  4986.5      .1       0  5120.2     .07       0  5335.3      .1       0
Bank Sta=4978,4986.5
XS Rating Curve= 0 ,0
Exp/Cntr=0.3,0.1

Type RM Length L Ch R = 1 ,12335   ,485,485,485
BEGIN DESCRIPTION:
Stream0009 26.0
END DESCRIPTION:
XS GIS Cut Line= 3
        1958425.     13927175.01        1958675.       13926775.
        1958625.     13926375.02
#Sta/Elev= 30
  4528.3 1752.61  4576.4 1743.86  4601.1  1734.8  4618.8 1724.78  4625.9 1723.11
    4688 1720.66  4769.5 1719.96  4852.2 1721.23  4888.9 1720.18  4910.1 1715.45
  4920.7 1714.59  4965.4 1716.57  4984.4 1716.35  5009.6 1710.17  5010.1 1709.67
  5018.2 1710.17  5022.8 1712.88    5029 1712.92  5038.2 1715.71  5044.1 1714.88
  5062.3  1721.7  5111.9 1721.67    5162 1722.61  5171.1 1724.11  5237.2 1723.58
  5296.9 1726.31  5355.5 1731.77  5364.6 1733.37  5382.7 1741.02  5403.1 1747.51
#Mann= 8 ,-1 , 0
  4528.3     .07       0  4769.5      .1       0  4965.4     .07       0
  5009.6     .05       0  5018.2     .07       0  5038.2    .035       0
  5111.9      .1       0  5237.2     .07       0
Bank Sta=5009.6,5018.2
XS Rating Curve= 0 ,0
Exp/Cntr=0.3,0.1

Type RM Length L Ch R = 1 ,11850   ,903,903,903
BEGIN DESCRIPTION:
Stream0009 25.0
END DESCRIPTION:
XS GIS Cut Line= 3
        1959125.       13926875.        1959125.       13926775.
        1958825.       13926375.
#Sta/Elev= 30
  4900.7 1730.73  4918.5  1730.1  4945.1 1727.17  4951.8 1723.96  4954.5 1720.21
  4957.1 1717.79    4963 1713.66  4966.5 1711.12  4975.1 1707.13  4991.8 1704.32
  4992.3 1703.82  5000.5 1704.32  5010.4 1707.77  5025.1 1708.28  5032.9 1709.71
  5065.1 1711.83  5102.4 1711.93  5117.5 1713.28  5231.7 1713.32  5254.2 1714.69
  5257.9 1714.14  5275.2  1716.4  5348.9 1719.62  5355.4 1720.69  5415.5  1723.9
  5432.8  1725.8  5443.2    1727  5460.4 1732.69  5477.4 1740.71  5500.7 1745.72
#Mann= 8 ,-1 , 0
  4900.7     .07       0    4963      .1       0  4991.8     .05       0
  5000.5      .1       0  5117.5     .07       0  5275.2    .035       0
  5415.5      .1       0  5432.8     .07       0
Bank Sta=4991.8,5000.5
XS Rating Curve= 0 ,0
Exp/Cntr=0.3,0.1

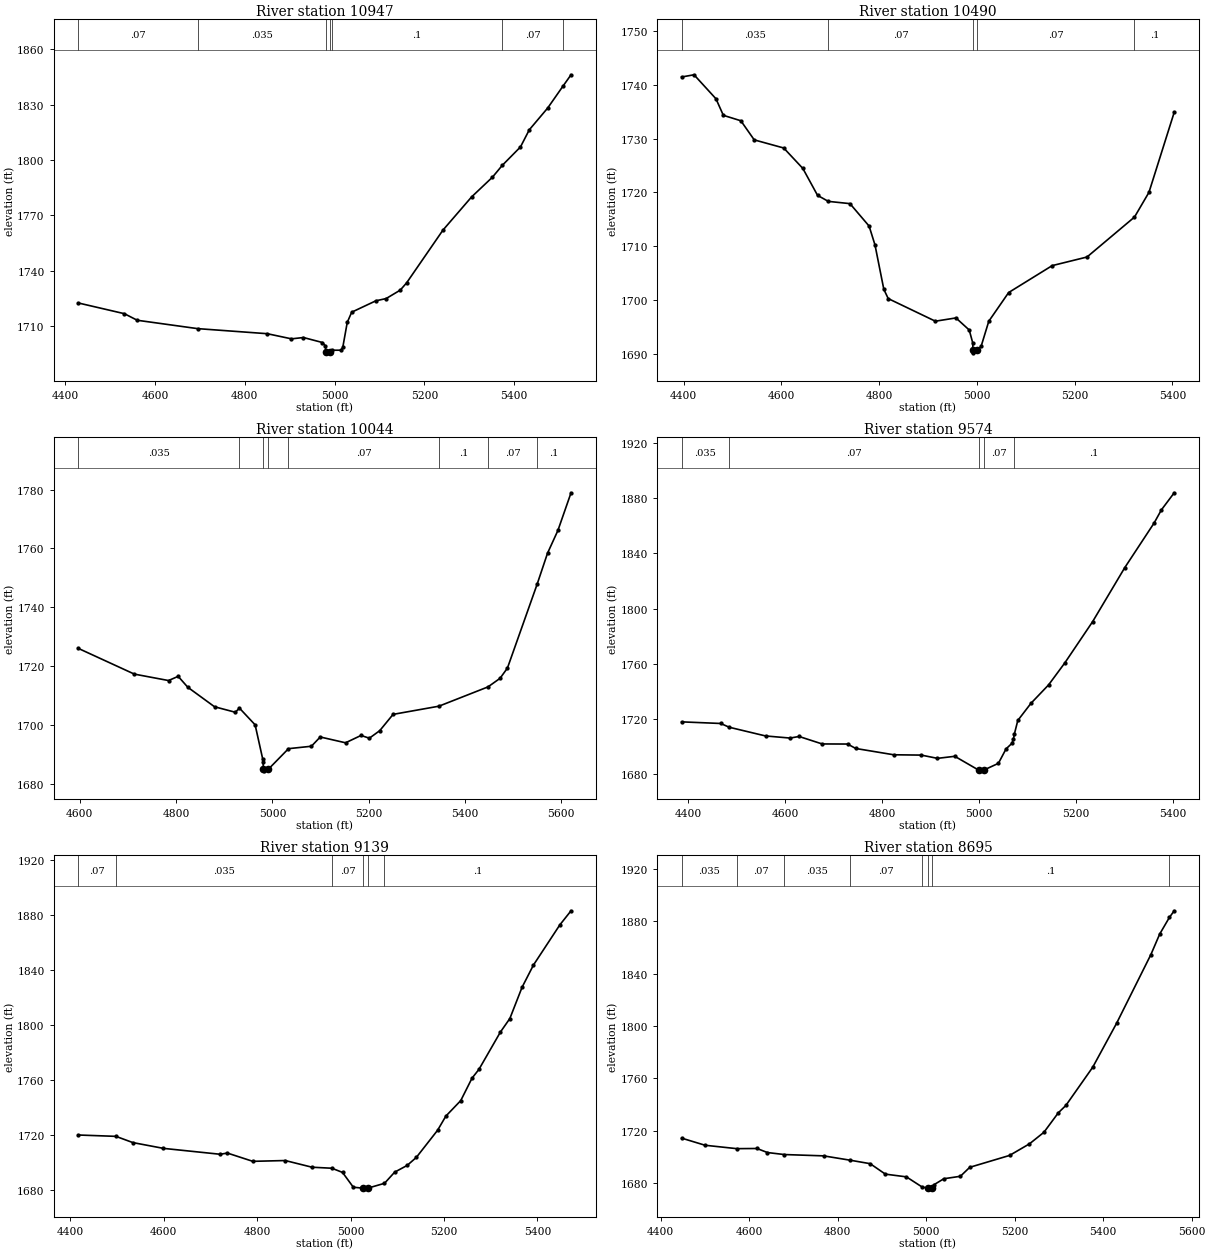
Type RM Length L Ch R = 1 ,10947   ,457,457,457
BEGIN DESCRIPTION:
Stream0009 24.0
END DESCRIPTION:
XS GIS Cut Line= 3
      1959275.01     13926774.99        1959675.       13926375.
      1960075.02     13926024.99
#Sta/Elev= 30
  4429.4 1722.47  4531.7 1716.68  4560.3 1713.12  4694.7 1708.59  4849.9 1705.84
  4903.9 1703.05  4930.5 1703.77  4972.9 1701.06  4979.2 1699.25    4981 1695.97
  4981.5 1695.47  4990.3 1695.97  4994.5 1696.89  5014.1  1696.9  5018.1 1698.39
  5028.1 1711.97    5038  1717.5  5091.9 1723.67  5114.7 1724.88  5146.1 1729.44
  5160.3 1733.38  5241.3 1761.98  5305.1 1779.96  5351.6 1790.67  5373.5 1797.08
    5414 1807.05  5433.6 1816.32  5474.6 1828.13  5508.2 1839.83  5526.6 1846.14
#Mann= 7 ,-1 , 0
  4429.4     .07       0  4694.7    .035       0    4981     .05       0
  4990.3    .035       0  4994.5      .1       0  5373.5     .07       0
  5508.2      .1       0
Bank Sta=4981,4990.3
XS Rating Curve= 0 ,0
Exp/Cntr=0.3,0.1

Type RM Length L Ch R = 1 ,10490   ,446,446,446
BEGIN DESCRIPTION:
Stream0009 23.0
END DESCRIPTION:
XS GIS Cut Line= 3
      1959819.31      13927368.1        1959875.       13926775.
        1959975.     13926375.02
#Sta/Elev= 30
  4395.9  1741.5  4421.2 1741.91  4466.1 1737.44  4481.2 1734.36    4517 1733.35
  4544.4 1729.79  4604.7 1728.28  4643.9 1724.47    4674 1719.46    4696 1718.34
  4740.3 1717.92  4779.5 1713.74  4791.5 1710.24  4809.6 1701.97  4818.6 1700.24
  4915.1 1696.03  4957.2 1696.64  4984.4 1694.39  4991.6 1691.98  4991.9 1690.64
  4992.4 1690.14  5001.2 1690.64  5008.9  1691.4  5024.4 1696.02  5065.1 1701.37
  5154.2 1706.38  5225.4 1707.98  5322.6 1715.42  5352.2 1720.02  5403.9 1734.93
#Mann= 5 ,-1 , 0
  4395.9    .035       0    4696     .07       0  4991.9     .05       0
  5001.2     .07       0  5322.6      .1       0
Bank Sta=4991.9,5001.2
XS Rating Curve= 0 ,0
Exp/Cntr=0.3,0.1

Type RM Length L Ch R = 1 ,10044   ,470,470,470
BEGIN DESCRIPTION:
Stream0009 22.0
END DESCRIPTION:
XS GIS Cut Line= 3
      1960413.19     13927181.08        1960225.       13926825.
      1960081.88     13926221.69
#Sta/Elev= 30
  4597.3  1726.1  4713.3  1717.4  4784.3 1715.22  4804.3 1716.64  4824.3 1712.94
  4879.8 1706.33  4922.9 1704.47  4931.6 1705.86  4964.1  1700.2  4979.7 1688.72
  4980.6 1687.73  4981.3  1685.1  4981.8  1684.6  4991.3  1685.1  5033.4 1692.12
    5081 1692.94  5099.3 1696.08  5151.9 1694.11    5184  1696.6  5201.3 1695.67
  5222.8 1698.21  5250.6 1703.75  5345.7 1706.52  5447.6 1713.06  5472.6 1715.96
    5488 1719.44  5549.5 1747.79  5571.3 1758.41  5592.8  1766.1  5620.1 1778.89
#Mann= 8 ,-1 , 0
  4597.3    .035       0  4931.6     .07       0  4981.3    .035       0
  4991.3     .07       0  5033.4     .07       0  5345.7      .1       0
  5447.6     .07       0  5549.5      .1       0
Bank Sta=4981.3,4991.3
XS Rating Curve= 0 ,0
Exp/Cntr=0.3,0.1

Type RM Length L Ch R = 1 ,9574    ,435,435,435
BEGIN DESCRIPTION:
Stream0009 21.0
END DESCRIPTION:
XS GIS Cut Line= 3
      1960715.48     13927057.68        1960525.       13926475.
        1960575.     13926075.04
#Sta/Elev= 30
  4386.5 1717.88  4467.1 1716.71  4484.6 1713.98  4559.5 1707.67    4610 1706.14
  4628.8 1707.28  4676.3 1701.87  4728.7  1701.8  4745.7 1698.58  4823.9 1694.02
  4880.9 1693.78  4914.2 1691.42  4949.9 1692.91  4999.3 1682.87  4999.8 1682.37
  5009.4 1682.87  5039.9  1687.8  5055.7 1698.29  5067.8 1702.31  5070.9 1705.26
  5072.6 1708.72  5079.9 1718.89  5107.1 1731.34  5143.4 1744.68  5176.7 1760.53
  5234.1 1790.45  5300.6 1829.72  5361.1 1862.05  5376.2 1871.62  5402.6 1883.98
#Mann= 5 ,-1 , 0
  4386.5    .035       0  4484.6     .07       0  4999.3     .05       0
  5009.4     .07       0  5072.6      .1       0
Bank Sta=4999.3,5009.4
XS Rating Curve= 0 ,0
Exp/Cntr=0.3,0.1

Type RM Length L Ch R = 1 ,9139    ,444,444,444
BEGIN DESCRIPTION:
Stream0009 20.0
END DESCRIPTION:
XS GIS Cut Line= 3
      1960993.79     13927053.81        1960925.       13926475.
      1960674.99     13926074.99
#Sta/Elev= 30
  4417.5 1719.93  4497.7 1718.95  4533.9 1714.42  4599.4 1710.21  4720.9 1705.92
  4736.3  1706.8  4790.7 1700.78  4860.2 1701.36  4917.6 1696.49    4960 1695.76
  4982.8 1692.72    5006 1681.93  5026.8 1681.27  5027.3 1680.77    5037 1681.27
  5072.7 1684.79  5094.5 1692.92  5121.2  1697.8  5140.8 1703.61  5186.4  1723.4
  5204.1 1733.69    5236 1744.99  5260.1 1761.29  5274.9 1767.67  5320.9 1794.84
  5341.1 1804.68  5367.2 1827.38  5391.6 1843.57  5448.2 1872.84  5472.1 1883.06
#Mann= 6 ,-1 , 0
  4417.5     .07       0  4497.7    .035       0    4960     .07       0
  5026.8     .05       0    5037     .07       0  5072.7      .1       0
Bank Sta=5026.8,5037
XS Rating Curve= 0 ,0
Exp/Cntr=0.3,0.1

Type RM Length L Ch R = 1 ,8695    ,454,454,454
BEGIN DESCRIPTION:
Stream0009 19.0
END DESCRIPTION:
XS GIS Cut Line= 3
      1961366.59     13926870.97        1961325.       13926325.
      1960925.03     13925925.03
#Sta/Elev= 30
  4447.4 1714.16  4500.3 1708.71  4571.9 1706.11  4617.6 1706.23  4641.2 1703.14
  4679.3  1701.6  4768.1 1700.59  4828.5 1697.25  4873.4 1694.61  4907.8  1686.6
  4955.3 1684.52  4990.8 1676.75  5003.5 1675.85    5004 1675.35  5013.7 1675.85
  5017.1 1678.39  5039.9 1683.08  5077.3 1684.96  5098.5 1691.83  5188.4 1700.91
  5233.5  1709.8  5266.1 1718.63  5298.7 1733.56  5315.7 1739.17  5376.4 1768.42
  5430.2 1801.98  5507.9 1854.68  5527.8 1870.37  5549.7 1883.11  5560.6 1888.18
#Mann= 8 ,-1 , 0
  4447.4    .035       0  4571.9     .07       0  4679.3    .035       0
  4828.5     .07       0  4990.8      .1       0  5003.5     .05       0
  5013.7      .1       0  5549.7     .07       0
Bank Sta=5003.5,5013.7
XS Rating Curve= 0 ,0
Exp/Cntr=0.3,0.1

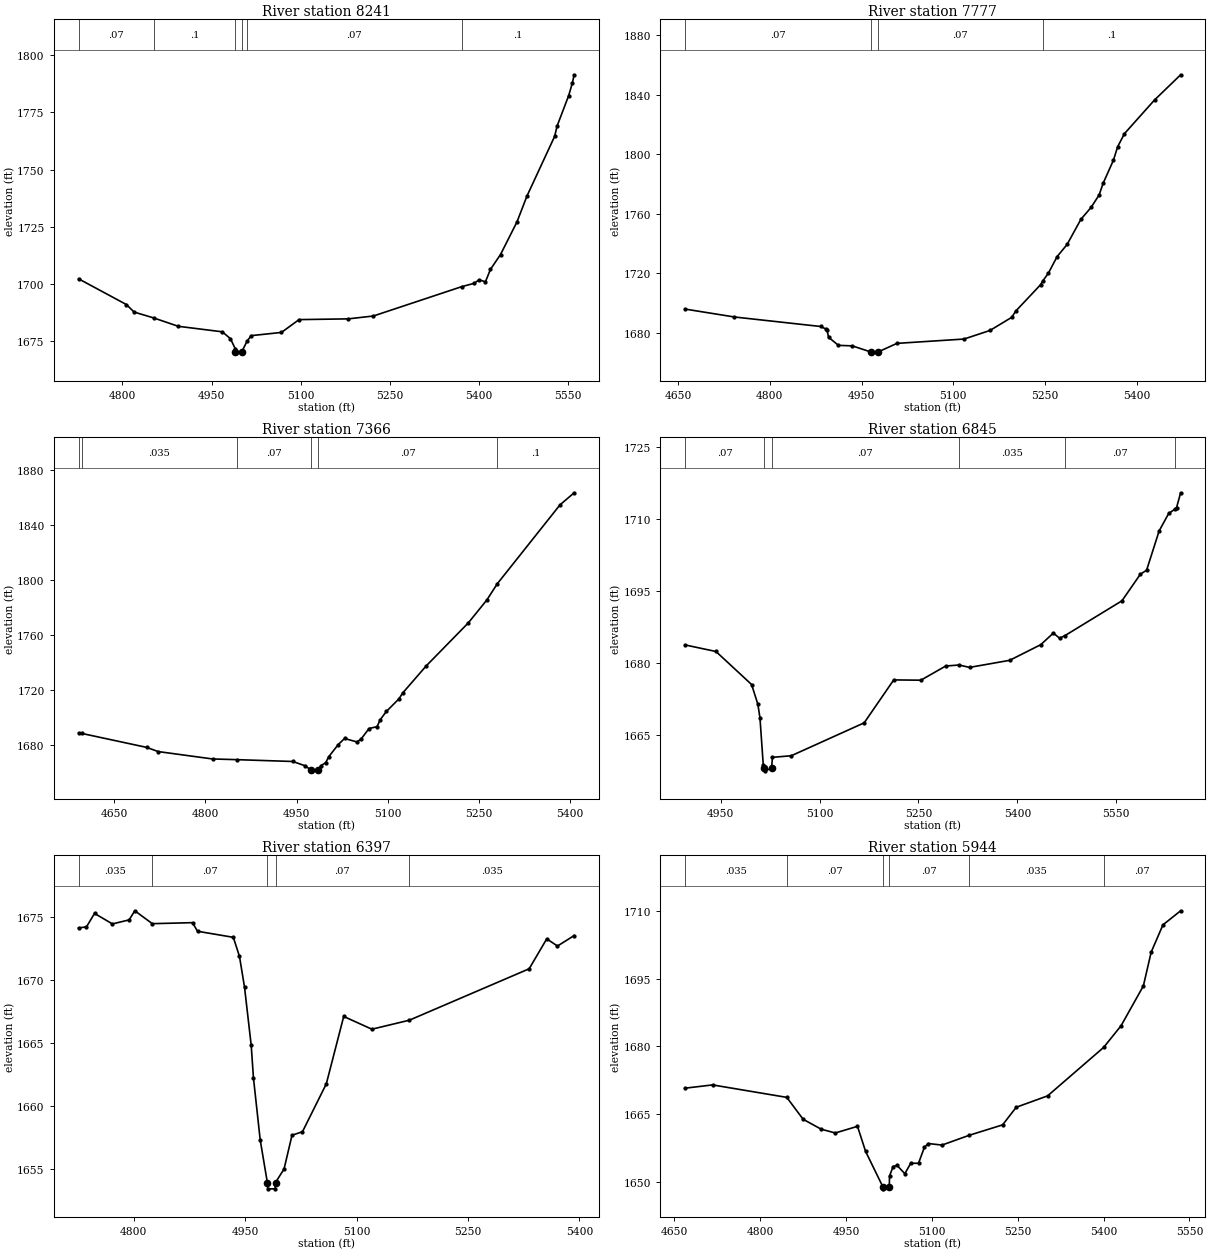
Type RM Length L Ch R = 1 ,8241    ,464,464,464
BEGIN DESCRIPTION:
Stream0009 18.0
END DESCRIPTION:
XS GIS Cut Line= 3
        1961825.       13926425.        1961725.       13926175.
      1961325.03     13925775.03
#Sta/Elev= 30
  4726.1  1702.2  4806.6 1690.95  4819.6 1687.66  4852.4 1685.11  4893.9 1681.44
  4968.2 1679.02  4981.9    1676  4990.2 1671.48  4990.3 1670.32  4990.8 1669.82
  5001.1 1670.32  5009.6 1674.82  5016.9 1677.35  5067.8 1678.75  5097.5 1684.36
  5180.3 1684.69  5222.7 1685.94  5371.5 1698.78  5392.3 1700.23  5400.9 1701.79
  5411.5  1700.9  5419.9 1706.33  5436.9 1712.84  5464.6 1727.09  5481.5 1738.46
  5528.1 1764.55  5532.3 1769.11  5551.5 1782.23  5557.8 1787.73    5561  1791.5
#Mann= 6 ,-1 , 0
  4726.1     .07       0  4852.4      .1       0  4990.3     .05       0
  5001.1      .1       0  5009.6     .07       0  5371.5      .1       0
Bank Sta=4990.3,5001.1
XS Rating Curve= 0 ,0
Exp/Cntr=0.3,0.1

Type RM Length L Ch R = 1 ,7777    ,411,411,411
BEGIN DESCRIPTION:
Stream0009 17.0
END DESCRIPTION:
XS GIS Cut Line= 3
      1962209.71      13926235.2        1962075.       13925925.
        1961825.     13925524.99
#Sta/Elev= 30
  4661.6 1695.88  4742.3 1690.56  4882.9 1684.19  4892.7 1682.32  4893.7 1681.62
    4896 1676.96  4912.3 1671.49  4934.8 1671.16  4965.8 1666.97  4966.3 1666.47
  4976.6 1666.97  5007.8 1672.83  5117.5 1675.74  5159.9 1681.52  5195.3  1690.3
  5202.4 1694.71  5242.5 1712.21  5246.2 1714.78  5255.4 1720.06  5269.6 1731.13
    5286 1739.35  5308.5 1756.21  5325.2 1764.25  5338.3  1772.6  5344.8 1780.41
  5361.6 1795.87  5368.6 1805.02  5379.7  1813.8  5428.8 1836.39  5471.5 1853.35
#Mann= 4 ,-1 , 0
  4661.6     .07       0  4965.8     .05       0  4976.6     .07       0
  5246.2      .1       0
Bank Sta=4965.8,4976.6
XS Rating Curve= 0 ,0
Exp/Cntr=0.3,0.1

Type RM Length L Ch R = 1 ,7366    ,521,521,521
BEGIN DESCRIPTION:
Stream0009 16.0
END DESCRIPTION:
XS GIS Cut Line= 3
        1962475.     13926074.99      1962378.77     13925687.19
      1962175.02     13925325.03
#Sta/Elev= 30
  4591.6 1688.57  4596.4 1688.26  4703.7 1678.05  4722.4 1675.02  4811.9 1669.64
  4851.6 1669.14  4943.9  1667.8  4963.3  1664.8  4974.5 1661.49    4975 1660.99
  4985.4 1661.49  4989.8 1664.61    4998 1666.99  5003.2 1671.38  5018.7 1680.17
    5029 1684.56  5049.5 1682.02  5056.5 1684.29  5069.3 1691.82  5082.5 1693.15
  5087.5 1698.11  5097.8 1704.25  5118.5 1713.41  5124.4 1717.56  5163.2 1737.35
  5232.7  1768.8  5263.1 1785.44  5280.3 1797.26  5383.5 1854.74  5406.7 1863.48
#Mann= 6 ,-1 , 0
  4591.6     .07       0  4596.4    .035       0  4851.6     .07       0
  4974.5     .05       0  4985.4     .07       0  5280.3      .1       0
Bank Sta=4974.5,4985.4
XS Rating Curve= 0 ,0
Exp/Cntr=0.3,0.1

Type RM Length L Ch R = 1 ,6845    ,448,448,448
BEGIN DESCRIPTION:
Stream0009 15.0
END DESCRIPTION:
XS GIS Cut Line= 3
        1962775.     13926024.99        1962775.       13925925.
      1962565.24     13925308.39
#Sta/Elev= 30
  4896.2 1683.72    4943 1682.35    4997 1675.46  5006.5 1671.35  5009.7 1668.52
  5014.7  1658.7  5016.3 1657.94  5016.8 1657.44  5027.2 1657.94  5028.7 1660.26
  5057.2 1660.59  5167.7 1667.46  5212.5 1676.42  5253.7 1676.36  5291.3 1679.32
  5311.7 1679.53  5327.4 1679.03  5388.3 1680.51  5435.5 1683.78  5454.5  1686.2
  5463.9 1685.13  5471.9 1685.65  5558.5 1692.93  5586.4 1698.47  5595.9 1699.32
  5614.9 1707.52  5629.4 1711.17  5638.5 1712.03  5641.3 1712.38  5647.5 1715.48
#Mann= 6 ,-1 , 0
  4896.2     .07       0  5016.3     .05       0  5027.2     .07       0
  5311.7    .035       0  5471.9     .07       0  5638.5      .1       0
Bank Sta=5016.3,5027.2
XS Rating Curve= 0 ,0
Exp/Cntr=0.3,0.1

Type RM Length L Ch R = 1 ,6397    ,453,453,453
BEGIN DESCRIPTION:
Stream0009 14.0
END DESCRIPTION:
XS GIS Cut Line= 3
      1963201.51     13926047.46        1963175.       13925775.
      1963051.16     13925401.76
#Sta/Elev= 30
  4725.9 1674.11  4736.4 1674.18  4747.3 1675.25  4771.4 1674.42  4793.9 1674.74
  4801.5 1675.46  4825.1 1674.44  4879.2 1674.52  4885.9 1673.84  4934.1 1673.36
  4942.4 1671.85  4949.2 1669.41  4958.2 1664.81  4961.2 1662.24  4970.3 1657.33
  4979.9 1653.96  4980.4 1653.46  4990.4 1653.46  4990.9 1653.96  5002.4 1655.03
  5013.1  1657.7  5027.2 1657.98  5059.3 1661.77  5082.7  1667.1  5120.6 1666.09
  5170.9  1666.8  5332.3 1670.87    5356 1673.24  5370.4 1672.67  5392.9  1673.5
#Mann= 5 ,-1 , 0
  4725.9    .035       0  4825.1     .07       0  4979.9     .05       0
  4990.9     .07       0  5170.9    .035       0
Bank Sta=4979.9,4990.9
XS Rating Curve= 0 ,0
Exp/Cntr=0.3,0.1

Type RM Length L Ch R = 1 ,5944    ,471,471,471
BEGIN DESCRIPTION:
Stream0009 13.0
END DESCRIPTION:
XS GIS Cut Line= 3
      1963404.56     13926004.22        1963575.       13925725.
      1963832.11     13925251.99
#Sta/Elev= 30
  4669.1 1670.79  4717.1 1671.51  4846.7 1668.76  4875.3 1663.92  4906.9 1661.73
  4931.5  1660.9  4970.2 1662.37  4984.3 1656.85  5014.3 1649.07  5014.8 1648.57
  5025.7 1649.07  5026.2 1651.42  5032.4 1653.49  5039.2 1653.77  5052.9  1651.9
  5063.1 1654.21  5076.8 1654.22    5087 1657.73  5093.9 1658.57  5117.8 1658.23
  5165.5  1660.4  5223.6 1662.69  5247.5 1666.58  5302.2 1669.09  5400.2  1679.8
  5430.6 1684.58  5469.5 1693.36  5483.1 1700.81  5503.7 1706.84  5534.6 1709.95
#Mann= 6 ,-1 , 0
  4669.1    .035       0  4846.7     .07       0  5014.3     .05       0
  5025.7     .07       0  5165.5    .035       0  5400.2     .07       0
Bank Sta=5014.3,5025.7
XS Rating Curve= 0 ,0
Exp/Cntr=0.3,0.1

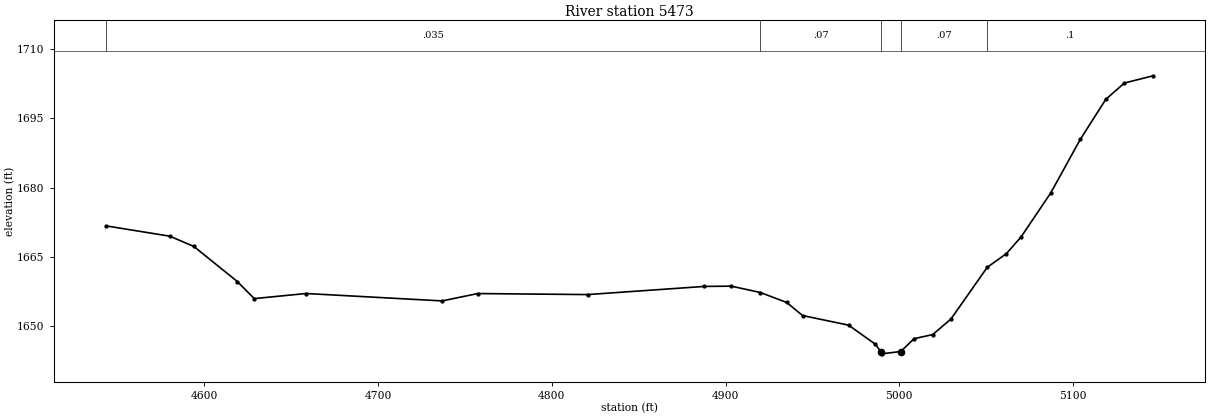
Type RM Length L Ch R = 1 ,5473    ,429,429,429
BEGIN DESCRIPTION:
Stream0009 12.0
END DESCRIPTION:
XS GIS Cut Line= 3
      1963624.99     13926125.01        1963975.       13925825.
      1964074.99     13925725.01
#Sta/Elev= 30
  4543.6 1671.73  4580.2 1669.51    4594  1667.3  4619.1  1659.7  4628.8 1656.02
  4658.6 1657.12  4736.9 1655.52  4757.4 1657.11  4820.6 1656.89  4887.8 1658.65
  4903.3 1658.71  4920.1 1657.33  4935.2 1655.18  4944.3 1652.36  4970.8 1650.28
  4986.2 1646.15  4989.3 1644.58  4989.8 1644.08  5000.8 1644.58  5008.5 1647.36
  5019.2 1648.24  5029.7 1651.61  5050.6 1662.79  5061.6 1665.73  5070.1 1669.38
  5087.1 1678.85  5104.1 1690.42  5118.8 1699.09  5129.5 1702.61    5146 1704.18
#Mann= 5 ,-1 , 0
  4543.6    .035       0  4920.1     .07       0  4989.3     .05       0
  5000.8     .07       0  5050.6      .1       0
Bank Sta=4989.3,5000.8
XS Rating Curve= 0 ,0
Exp/Cntr=0.3,0.1