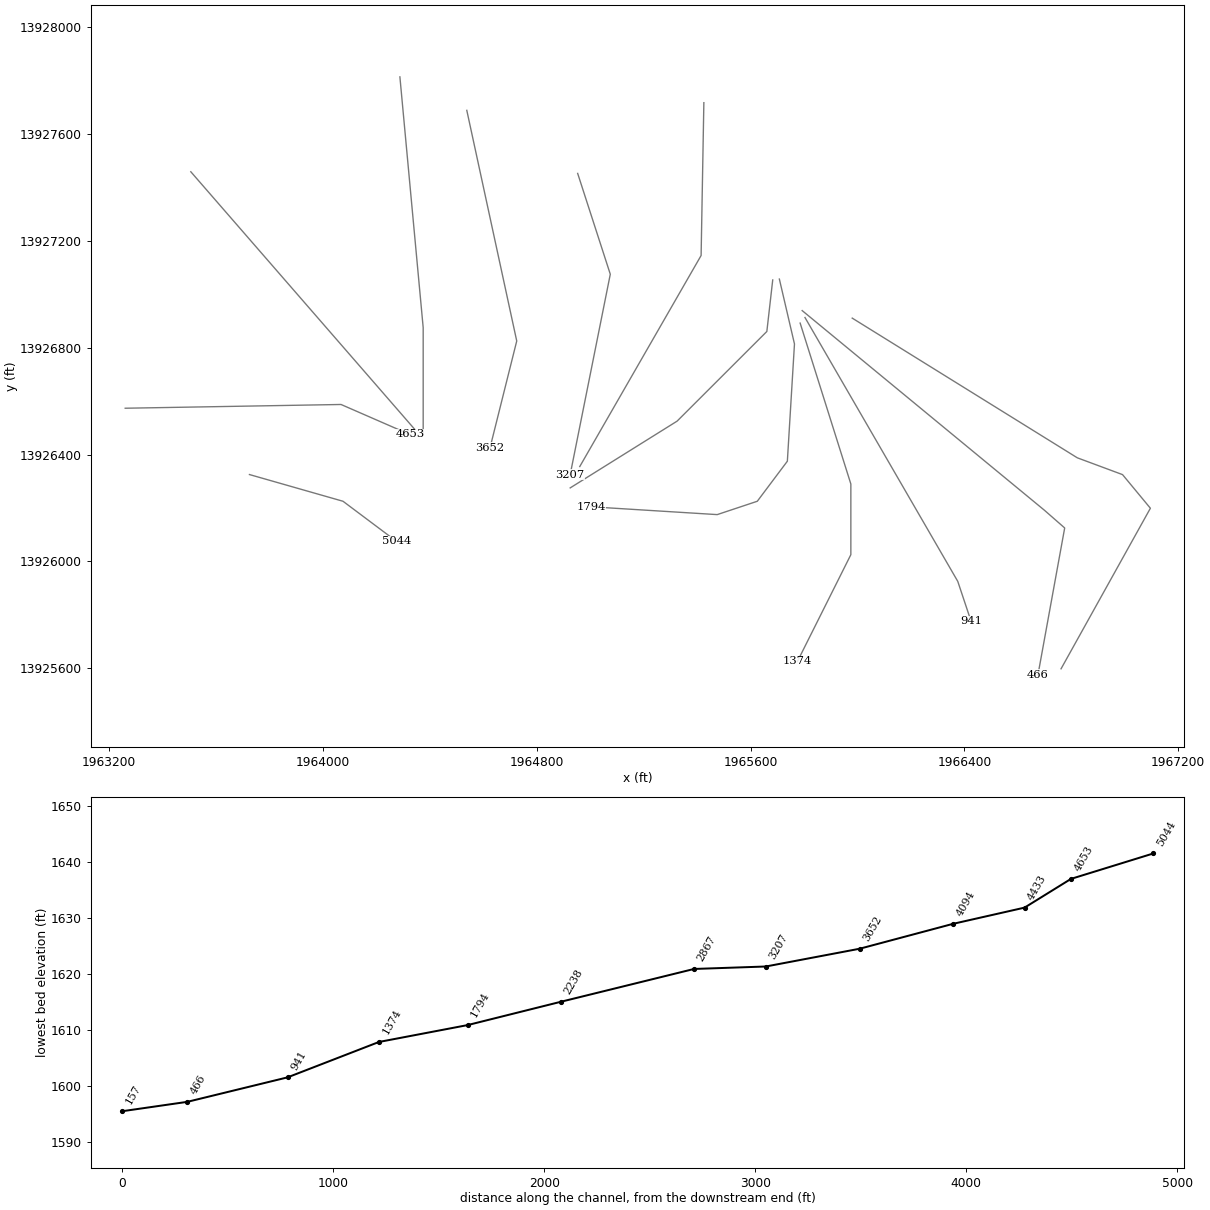
HEC-RAS study Stream0009.prj: Stream0009 Base Level Engineering

--- Stream0009.g01 (geometry) --- (continued)

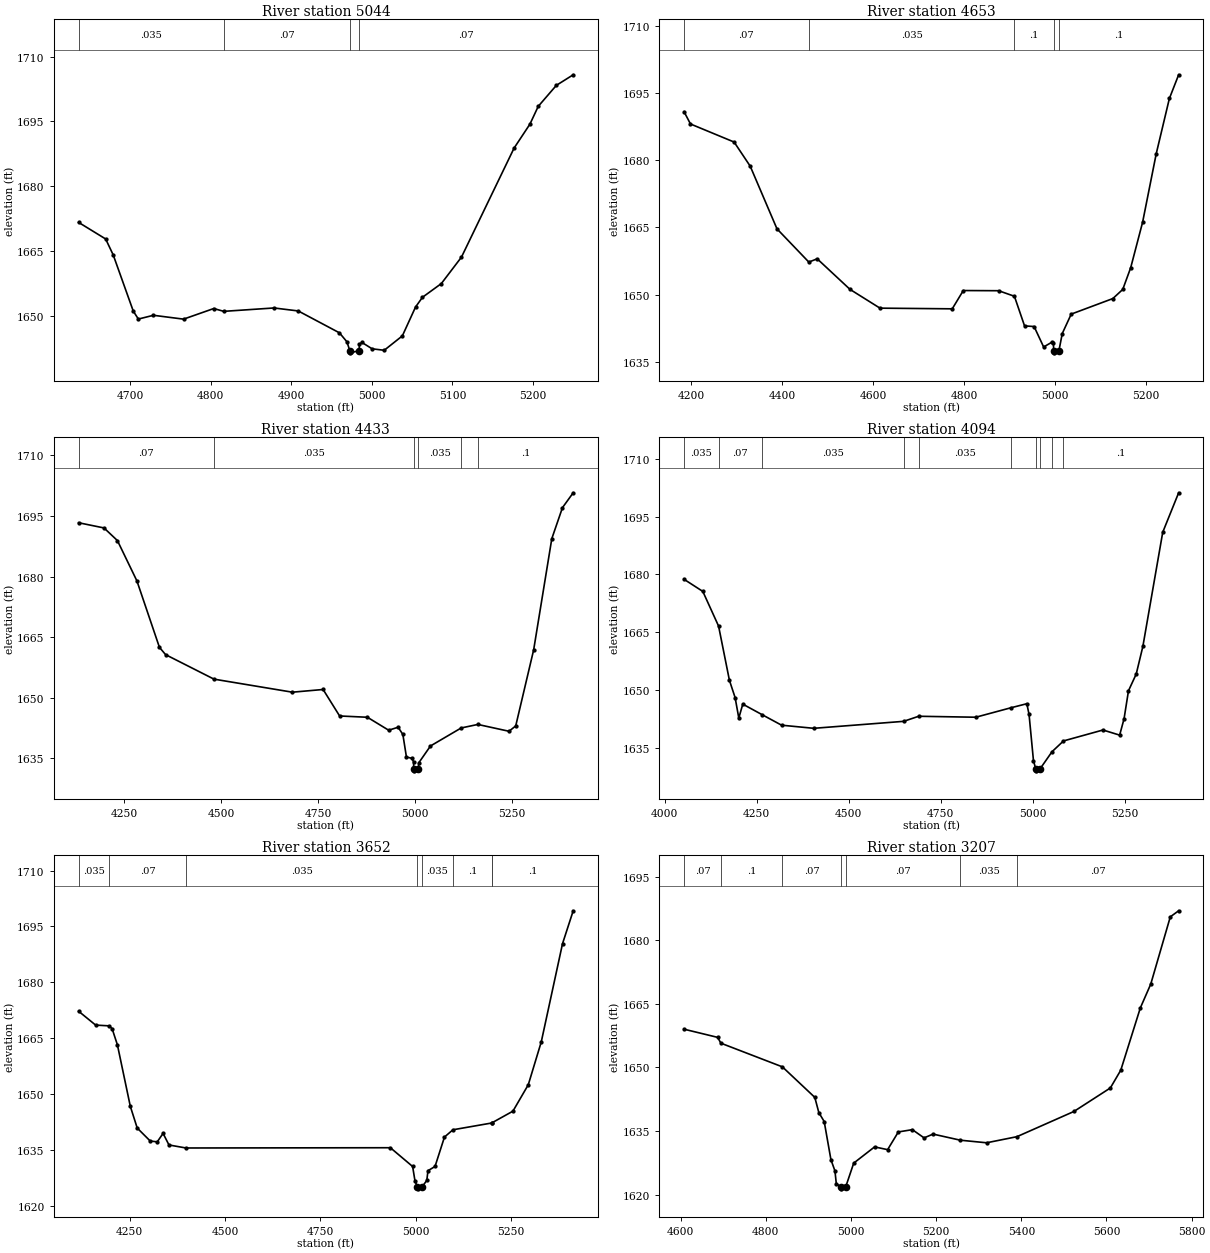
Type RM Length L Ch R = 1 ,5044    ,391,391,391
BEGIN DESCRIPTION:
Stream0009 11.0
END DESCRIPTION:
XS GIS Cut Line= 3
      1963725.03     13926324.99        1964075.       13926225.
      1964275.02     13926074.99
#Sta/Elev= 30
  4635.9  1671.7  4669.5 1667.87  4678.9 1664.18  4703.8 1651.21  4710.1 1649.38
  4728.8 1650.25  4766.2 1649.36  4803.7 1651.81  4816.1 1651.16  4878.5 1651.94
  4908.6 1651.25  4959.7  1646.2    4969 1644.13  4972.6 1642.08  4973.1 1641.58
  4984.1 1642.08  4984.6 1643.61  4987.7 1643.97  5000.3 1642.51  5015.3 1642.17
  5037.8 1645.49  5054.2 1652.16  5062.8 1654.41  5086.2 1657.57  5111.2 1663.68
  5176.5 1688.85  5196.2 1694.39  5206.5 1698.49    5229 1703.34  5249.9 1705.78
#Mann= 4 ,-1 , 0
  4635.9    .035       0  4816.1     .07       0  4972.6     .05       0
  4984.1     .07       0
Bank Sta=4972.6,4984.1
XS Rating Curve= 0 ,0
Exp/Cntr=0.3,0.1

Type RM Length L Ch R = 1 ,4653    ,220,220,220
BEGIN DESCRIPTION:
Stream0009 10.0
END DESCRIPTION:
XS GIS Cut Line= 3
      1963260.17      13926573.3      1964067.61     13926587.34
        1964325.       13926475.
#Sta/Elev= 30
    4184 1690.83  4198.2 1688.08  4294.2 1684.05  4329.6 1678.67  4388.5 1664.69
  4458.6 1657.27    4477    1658  4549.2 1651.18  4615.2 1646.99  4774.2 1646.84
  4798.5 1650.92  4876.3 1650.88    4911 1649.64  4933.3 1643.03  4954.3 1642.89
  4975.3 1638.33  4993.4 1639.39  4996.7 1639.16  4997.5 1637.52    4998 1637.02
    5009 1637.52  5016.3 1641.33    5036 1645.66  5127.6 1649.13  5149.4 1651.17
  5166.9 1656.02  5193.1 1666.17  5223.1 1681.46    5252 1693.77  5272.4 1699.06
#Mann= 5 ,-1 , 0
    4184     .07       0  4458.6    .035       0    4911      .1       0
  4997.5     .05       0    5009      .1       0
Bank Sta=4997.5,5009
XS Rating Curve= 0 ,0
Exp/Cntr=0.3,0.1

Type RM Length L Ch R = 1 ,4433    ,339,339,339
BEGIN DESCRIPTION:
Stream0009 9.1
END DESCRIPTION:
XS GIS Cut Line= 2
      1963505.64     13927458.73       1964342.5     13926495.22
#Sta/Elev= 30
    4132 1693.33  4197.6 1692.04  4232.2 1688.91  4282.5 1678.92  4340.6 1662.47
  4356.5 1660.66  4481.4 1654.59  4683.6 1651.36  4762.9 1652.03  4805.5 1645.47
  4877.2 1645.15  4932.1 1641.94  4956.5 1642.68  4968.7 1640.89  4977.9 1635.31
  4992.3 1634.97  4996.2 1634.12  4996.8 1632.38  4997.3 1631.88  5008.4 1632.38
  5009.9 1633.89    5040 1638.04  5119.2  1642.5  5162.2 1643.37  5242.6 1641.68
  5259.9 1643.01  5306.2 1661.86    5353 1689.39  5380.5 1697.07  5408.2 1700.75
#Mann= 6 ,-1 , 0
    4132     .07       0  4481.4    .035       0  4996.8    .035       0
  5008.4    .035       0  5119.2     .07       0  5162.2      .1       0
Bank Sta=4996.8,5008.4
XS Rating Curve= 0 ,0
Exp/Cntr=0.3,0.1

Type RM Length L Ch R = 1 ,4094    ,442,442,442
BEGIN DESCRIPTION:
Stream0009 9.0
END DESCRIPTION:
XS GIS Cut Line= 3
      1964287.87       13927814.        1964375.       13926875.
        1964375.     13926475.03
#Sta/Elev= 30
  4052.7 1678.75  4103.7  1675.6  4146.5 1666.59    4176 1652.48  4191.4 1648.01
  4201.4  1642.7  4212.2 1646.31  4264.2  1643.6  4317.6 1640.84    4405 1640.03
  4648.9 1641.84  4689.9 1643.16  4844.9 1642.91  4939.2 1645.34  4983.5 1646.42
  4989.5 1643.64  5001.5 1631.62  5007.7 1629.48  5008.2 1628.98  5019.3 1629.48
  5051.8 1633.94    5083 1636.75  5190.2 1639.59  5235.5 1638.26  5247.5 1642.53
  5259.5 1649.79  5280.5 1654.13  5298.5 1661.29  5352.5 1690.98  5395.7 1701.23
#Mann= 10 ,-1 , 0
  4052.7    .035       0  4146.5     .07       0  4264.2    .035       0
  4648.9     .07       0  4689.9    .035       0  4939.2     .07       0
  5007.7     .05       0  5019.3     .07       0  5051.8    .035       0
    5083      .1       0
Bank Sta=5007.7,5019.3
XS Rating Curve= 0 ,0
Exp/Cntr=0.3,0.1

Type RM Length L Ch R = 1 ,3652    ,445,445,445
BEGIN DESCRIPTION:
Stream0009 8.0
END DESCRIPTION:
XS GIS Cut Line= 3
      1964538.15     13927688.64        1964725.       13926825.
      1964625.01     13926425.04
#Sta/Elev= 30
  4116.3 1672.23    4161  1668.5  4196.1  1668.3  4204.1 1667.56    4218  1663.2
  4251.8  1646.7  4269.9 1640.86    4304 1637.37  4322.4 1637.15  4337.7 1639.42
  4353.1 1636.31  4397.7  1635.5  4933.2 1635.57  4991.5 1630.53  4997.7 1626.64
  5004.2 1625.03  5004.7 1624.53  5015.9 1625.03  5028.6 1626.78  5031.7  1629.4
  5050.2 1630.54  5074.9 1638.44  5097.1 1640.39  5199.3 1642.22  5200.6 1642.33
  5254.3 1645.39  5294.5 1652.48  5328.5 1663.98  5384.2 1690.36  5412.2  1699.2
#Mann= 8 ,-1 , 0
  4116.3    .035       0  4196.1     .07       0  4397.7    .035       0
  5004.2    .035       0  5015.9    .035       0  5097.1      .1       0
  5199.3     .07       0  5200.6      .1       0
Bank Sta=5004.2,5015.9
XS Rating Curve= 0 ,0
Exp/Cntr=0.3,0.1

Type RM Length L Ch R = 1 ,3207    ,340,340,340
BEGIN DESCRIPTION:
Stream0009 7.0
END DESCRIPTION:
XS GIS Cut Line= 3
      1964952.96     13927452.47        1965075.       13927075.
      1964924.99     13926324.96
#Sta/Elev= 30
  4607.9 1659.03  4686.9  1657.1  4694.4 1655.73  4838.9 1650.14    4915 1642.94
  4924.5 1639.34  4937.1 1637.23  4952.9 1628.22  4962.3 1625.59  4965.5 1622.57
  4975.7 1621.85  4976.2 1621.35  4987.7 1621.85  5006.4 1627.42  5055.4 1631.25
    5086  1630.6  5111.2 1634.78  5144.1 1635.32  5171.6 1633.38  5192.8 1634.27
  5256.8 1632.83  5318.5 1632.22  5389.7 1633.66  5523.5 1639.61  5609.1 1645.16
  5633.6 1649.36  5679.5 1664.05    5704 1669.68  5749.9 1685.55  5769.5 1686.98
#Mann= 7 ,-1 , 0
  4607.9     .07       0  4694.4      .1       0  4838.9     .07       0
  4975.7     .05       0  4987.7     .07       0  5256.8    .035       0
  5389.7     .07       0
Bank Sta=4975.7,4987.7
XS Rating Curve= 0 ,0
Exp/Cntr=0.3,0.1

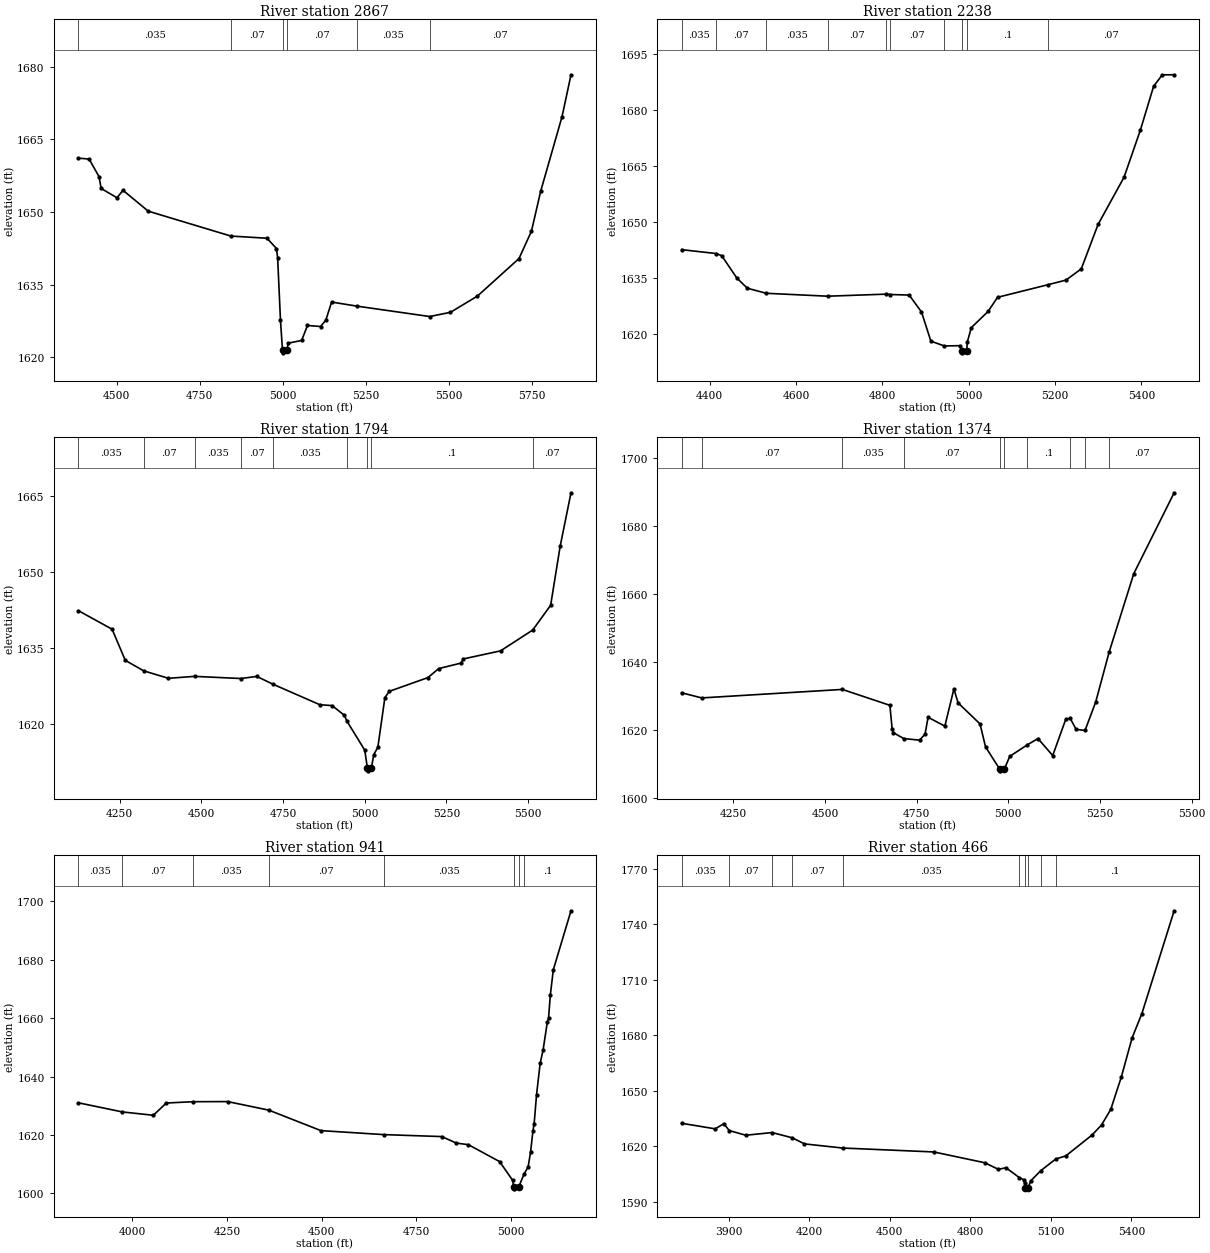
Type RM Length L Ch R = 1 ,2867    ,629,629,629
BEGIN DESCRIPTION:
Stream0009 6.0
END DESCRIPTION:
XS GIS Cut Line= 3
      1965425.06     13927717.35      1965414.78     13927145.15
      1964960.82     13926354.96
#Sta/Elev= 30
  4384.6 1661.12  4416.7 1660.93  4446.7 1657.27  4452.7 1654.87  4500.7 1652.94
  4518.7 1654.48  4594.8 1650.17  4843.6 1645.03  4952.4 1644.58    4981 1642.46
  4984.5 1640.56  4993.1 1627.59  4999.2 1621.41  4999.7 1620.91  5011.3 1621.41
  5017.2 1622.92  5056.8 1623.46  5074.4 1626.56  5113.9 1626.35  5129.8 1627.68
  5147.1  1631.4    5224 1630.55  5442.6 1628.41  5505.1 1629.28  5586.5 1632.64
  5711.6 1640.39  5749.1 1646.03  5776.8 1654.27  5841.3 1669.71  5868.2 1678.34
#Mann= 6 ,-1 , 0
  4384.6    .035       0  4843.6     .07       0  4999.2     .05       0
  5011.3     .07       0    5224    .035       0  5442.6     .07       0
Bank Sta=4999.2,5011.3
XS Rating Curve= 0 ,0
Exp/Cntr=0.3,0.1

Type RM Length L Ch R = 1 ,2238    ,444,444,444
BEGIN DESCRIPTION:
Stream0009 5.0
END DESCRIPTION:
XS GIS Cut Line= 4
      1965682.71     13927053.59      1965660.71     13926860.71
        1965325.       13926525.        1964925.       13926275.
#Sta/Elev= 30
  4335.2 1642.66  4415.4 1641.62    4428 1641.05  4463.4 1635.02  4487.6 1632.33
  4531.4 1630.99  4673.3 1630.21  4808.4 1630.76  4818.7 1630.66  4862.2 1630.52
  4890.7 1625.99  4912.5 1618.18  4943.6  1616.9  4980.4 1616.98  4983.4 1615.56
  4983.9 1615.06  4995.5 1615.56  4996.7  1617.9  5006.1  1621.8    5045 1626.14
  5066.8 1629.91  5184.2  1633.3  5225.4 1634.52  5260.8 1637.53  5299.7 1649.42
  5359.8 1662.03  5397.8  1674.7  5428.2 1686.33  5448.3 1689.43  5475.8 1689.44
#Mann= 10 ,-1 , 0
  4335.2    .035       0  4415.4     .07       0  4531.4    .035       0
  4673.3     .07       0  4808.4      .1       0  4818.7     .07       0
  4943.6      .1       0  4983.4     .05       0  4995.5      .1       0
  5184.2     .07       0
Bank Sta=4983.4,4995.5
XS Rating Curve= 0 ,0
Exp/Cntr=0.3,0.1

Type RM Length L Ch R = 1 ,1794    ,420,420,420
BEGIN DESCRIPTION:
Stream0009 4.0
END DESCRIPTION:
XS GIS Cut Line= 6
      1965707.52     13927056.93      1965764.07     13926813.95
      1965737.45     13926374.93        1965625.       13926225.
        1965475.       13926175.      1965003.14     13926204.28
#Sta/Elev= 30
  4123.6 1642.38  4226.5 1638.74    4267  1632.6  4323.6 1630.54  4398.9 1629.08
  4478.8 1629.46  4620.5 1629.04  4669.4 1629.45  4719.2 1627.91  4862.5 1623.88
    4900 1623.71  4937.8 1621.78  4945.2 1620.66  4999.9 1614.94  5008.1 1611.37
  5008.6 1610.87  5020.2 1611.37  5027.4 1614.06    5040 1615.51  5061.5 1625.27
  5074.8 1626.51  5193.2 1629.22  5226.2 1630.99  5295.4 1632.09  5301.4 1632.89
  5415.6 1634.48  5513.9 1638.57  5568.9 1643.45  5597.9 1655.02  5631.2 1665.59
#Mann= 9 ,-1 , 0
  4123.6    .035       0  4323.6     .07       0  4478.8    .035       0
  4620.5     .07       0  4719.2    .035       0  4945.2      .1       0
  5008.1     .05       0  5020.2      .1       0  5513.9     .07       0
Bank Sta=5008.1,5020.2
XS Rating Curve= 0 ,0
Exp/Cntr=0.3,0.1

Type RM Length L Ch R = 1 ,1374    ,433,433,433
BEGIN DESCRIPTION:
Stream0009 3.0
END DESCRIPTION:
XS GIS Cut Line= 4
       1965785.3     13926892.05        1965975.     13926289.57
        1965975.       13926025.      1965775.01     13925625.02
#Sta/Elev= 30
  4108.8 1630.82  4163.6 1629.31  4547.1 1631.81  4676.9 1627.13  4683.1 1620.08
  4686.3 1619.08  4714.9 1617.35  4757.8 1616.87  4772.8 1618.66  4781.1 1623.61
  4826.8 1621.01  4851.5 1631.97  4862.8 1627.87  4922.8 1621.64  4937.8 1614.89
  4976.5 1608.35    4977 1607.85  4989.1 1608.35  5003.8 1612.11  5051.6 1615.49
  5080.8 1617.35    5121 1612.35  5156.6 1623.03  5168.7  1623.3  5184.8 1620.06
  5209.2 1619.73  5238.4 1628.15    5275 1642.82  5342.2  1665.9  5452.2 1689.68
#Mann= 10 ,-1 , 0
  4108.8    .035       0  4163.6     .07       0  4547.1    .035       0
  4714.9     .07       0  4976.5     .05       0  4989.1     .07       0
  5051.6      .1       0  5168.7     .07       0  5209.2      .1       0
    5275     .07       0
Bank Sta=4976.5,4989.1
XS Rating Curve= 0 ,0
Exp/Cntr=0.3,0.1

Type RM Length L Ch R = 1 ,941     ,475,475,475
BEGIN DESCRIPTION:
Stream0009 2.0
END DESCRIPTION:
XS GIS Cut Line= 3
      1965803.41     13926912.94        1966375.       13925925.
        1966425.     13925774.99
#Sta/Elev= 30
  3858.6    1631  3974.7 1627.87  4056.1 1626.73  4090.3 1630.93  4160.6 1631.38
  4252.2 1631.42  4360.8 1628.49  4498.3 1621.47  4664.7  1620.1  4817.2 1619.43
  4855.3 1617.21  4887.4 1616.65  4969.7 1610.86  5004.2 1604.44  5007.1 1602.02
  5007.6 1601.52  5019.8 1602.02  5033.8 1606.45  5045.1 1609.08  5051.4 1614.11
  5057.7 1621.35  5060.9 1623.86  5067.2 1633.76  5076.7 1644.49  5084.5 1649.12
  5095.7  1658.7  5098.8 1659.92  5103.5 1667.83  5111.5 1676.62  5158.1 1696.81
#Mann= 8 ,-1 , 0
  3858.6    .035       0  3974.7     .07       0  4160.6    .035       0
  4360.8     .07       0  4664.7    .035       0  5007.1    .035       0
  5019.8    .035       0  5033.8      .1       0
Bank Sta=5007.1,5019.8
XS Rating Curve= 0 ,0
Exp/Cntr=0.3,0.1

Type RM Length L Ch R = 1 ,466     ,309,309,309
BEGIN DESCRIPTION:
Stream0009 1.0
END DESCRIPTION:
XS GIS Cut Line= 4
      1965792.91     13926938.86      1966698.94     13926191.56
        1966775.       13926125.      1966675.01     13925575.04
#Sta/Elev= 30
  3724.7 1632.53  3849.8 1629.53  3882.1 1632.32  3902.2 1628.59  3963.8 1626.08
  4061.7 1627.52  4136.6 1624.71  4182.2 1621.41  4324.2 1619.17  4663.7 1617.06
  4853.5 1611.24  4904.6 1607.67  4932.9 1608.53  4982.4 1603.23  4999.9 1601.97
  5002.3 1600.14  5002.8 1597.64  5003.3 1597.14  5015.6 1597.64  5024.4 1601.33
  5062.3 1606.94  5118.6 1613.28  5155.5  1614.9  5253.1 1626.15  5288.7 1631.58
  5323.2 1640.06  5362.9  1657.7  5402.5 1678.59  5439.1 1691.75  5559.2 1747.25
#Mann= 10 ,-1 , 0
  3724.7    .035       0  3902.2     .07       0  4061.7    .035       0
  4136.6     .07       0  4324.2    .035       0  4982.4    .035       0
  5002.8    .035       0  5015.6    .035       0  5062.3    .035       0
  5118.6      .1       0
Bank Sta=5002.8,5015.6
XS Rating Curve= 0 ,0
Exp/Cntr=0.3,0.1

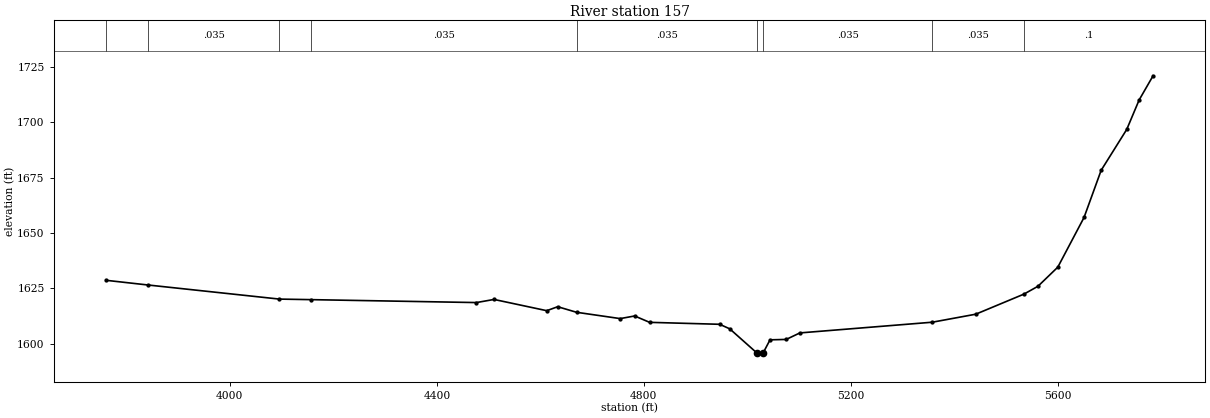
Type RM Length L Ch R = 1 ,157     ,0,0,0
BEGIN DESCRIPTION:
Stream0009 0.0
END DESCRIPTION:
XS GIS Cut Line= 5
      1965980.18     13926910.66       1966822.2     13926387.66
      1966991.47     13926324.72      1967095.63     13926198.85
      1966761.43     13925597.71
#Sta/Elev= 30
  3761.1 1628.63  3841.4 1626.53  4095.8 1620.16  4157.2 1619.91  4476.5 1618.59
  4510.6    1620  4612.4 1614.93  4633.6 1616.72    4670 1614.21  4754.3 1611.36
  4782.3 1612.54  4811.2 1609.67  4946.6 1608.79    4966 1606.75    5018 1595.96
  5018.5 1595.46  5030.8 1595.96  5043.9 1601.78  5075.1 1601.96  5101.6  1604.9
  5357.5 1609.73  5441.4 1613.34  5534.5  1622.4  5561.6 1625.93    5600 1634.57
  5650.7 1656.98  5683.8 1678.28  5733.2  1696.7  5757.2 1710.01  5784.1 1720.91
#Mann= 9 ,-1 , 0
  3761.1     .07       0  3841.4    .035       0  4095.8     .07       0
  4157.2    .035       0    4670    .035       0    5018    .035       0
  5030.8    .035       0  5357.5    .035       0  5534.5      .1       0
Bank Sta=5018,5030.8
XS Rating Curve= 0 ,0
Exp/Cntr=0.3,0.1

Chan Stop Cuts=-1
Use User Specified Reach Order=0
Composite Channel Slope=5