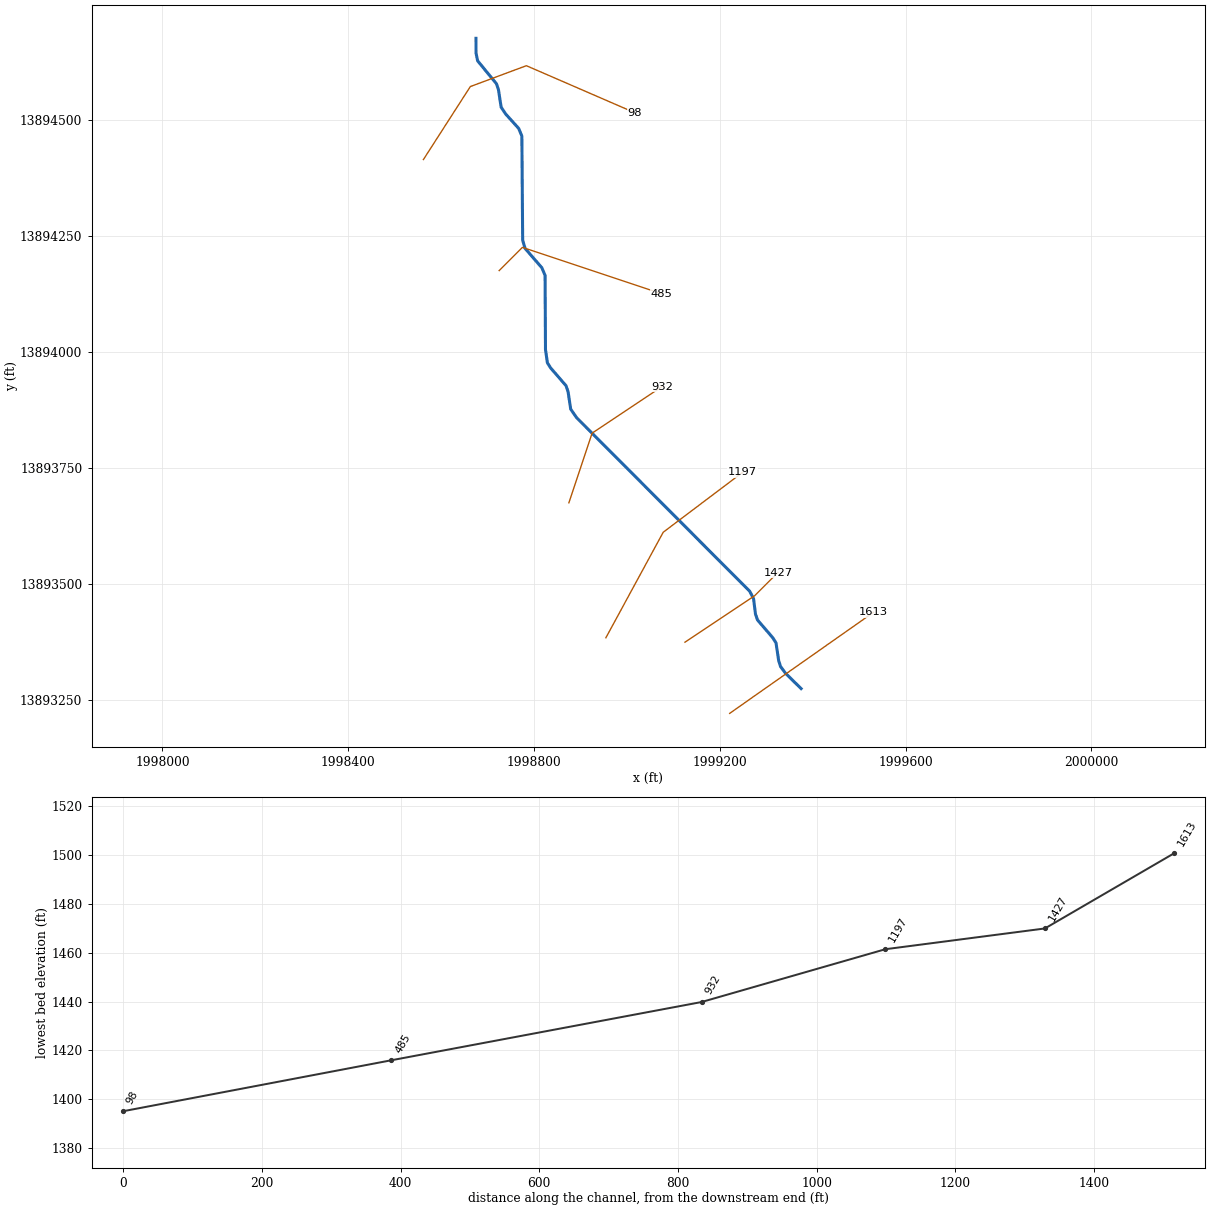
--- Stream0012.prj (project) ---

Proj Title=Stream0012 Base Level Engineering
Current Plan=p01
Default Exp/Contr=0.3,0.1
English Units
Geom File=g01
Flow File=f01
Plan File=p01
Y Axis Title=Elevation
X Axis Title(PF)=Main Channel Distance
X Axis Title(XS)=Station
BEGIN DESCRIPTION:
Stream0012
END DESCRIPTION:
DSS Export Rating Curves= 0
DSS Export Rating Curve Sorted= 0
DSS Export Volume Flow Curves= 0
DXF OffsetX= 0
DXF OffsetY= 0
DXF ScaleX= 1
DXF ScaleY= 10

--- Stream0012.p01 (plan) ---

Plan Title=Multiple Run
Short Identifier=Multiple
Geom File=g01
Flow File=f01
Subcritical Flow
K Sum by GR= 0
Std Step Tol= 0.01
Critical Tol= 0.01
Num of Std Step Trials= 20
Max Error Tol= 0.3
Flow Tol Ratio= 0.001
Split Flow NTrial= 30
Split Flow Tol= 0.02
Split Flow Ratio= 0.02
Log Output Level= 0
Friction Slope Method= 1
Unsteady Friction Slope Method= 2
Unsteady Bridges Friction Slope Method= 1
Parabolic Critical Depth
Global Vel Dist=  1 , 1 , 1
Global Log Level= 0
CheckData=True
Encroach Param= -1, 0, 0, 0
BEGIN DESCRIPTION:
Multiple Run
END DESCRIPTION:

--- Stream0012.f01 (steady flow) ---

Flow Title=Multiple
Number of Profiles=7
Profile Names=10-year,25-year,50-year,1pct_min,100-year,1pct_plu,500-year
River Rch & RM= Stream0012,Reach-1,1613
      66      90     110      66     131     261     181
River Rch & RM= Stream0012,Reach-1,1197
     144     214     272     170     339     677     515
Boundary for River Rch & Prof#=Stream0012,Reach-1,1
Up Type=0
Dn Type=3
Dn Slope=0.005
Boundary for River Rch & Prof#=Stream0012,Reach-1,2
Up Type=0
Dn Type=3
Dn Slope=0.005
Boundary for River Rch & Prof#=Stream0012,Reach-1,3
Up Type=0
Dn Type=3
Dn Slope=0.005
Boundary for River Rch & Prof#=Stream0012,Reach-1,4
Up Type=0
Dn Type=3
Dn Slope=0.005
Boundary for River Rch & Prof#=Stream0012,Reach-1,5
Up Type=0
Dn Type=3
Dn Slope=0.005
Boundary for River Rch & Prof#=Stream0012,Reach-1,6
Up Type=0
Dn Type=3
Dn Slope=0.005
Boundary for River Rch & Prof#=Stream0012,Reach-1,7
Up Type=0
Dn Type=3
Dn Slope=0.005

--- Stream0012.g01 (geometry) ---

Geom Title=Existing Conditions
Program Version=4.10

River Reach=Stream0012      ,Reach-1
Reach XY= 30
        1999375.       13893275.      1999341.41     13893308.07
      1999330.67     13893322.64       1999326.6     13893335.66
      1999320.96     13893373.33      1999313.96     13893384.57
       1999281.1     13893422.81       1999276.7      13893435.7
       1999272.5     13893468.97      1999264.24     13893484.68
      1998891.64     13893858.32      1998878.94     13893876.63
      1998873.28     13893914.29      1998868.86     13893927.17
      1998835.79     13893965.33      1998828.75     13893976.55
      1998824.64     13894004.85      1998823.78     13894164.49
      1998816.86     13894181.06      1998780.75     13894222.67
      1998775.52     13894240.22       1998773.8      13894464.5
      1998766.91     13894481.08      1998739.04     13894511.96
      1998729.17     13894526.73      1998723.39     13894564.33
      1998719.05     13894577.25       1998678.6     13894626.49
       1998675.1     13894643.19        1998675.       13894675.

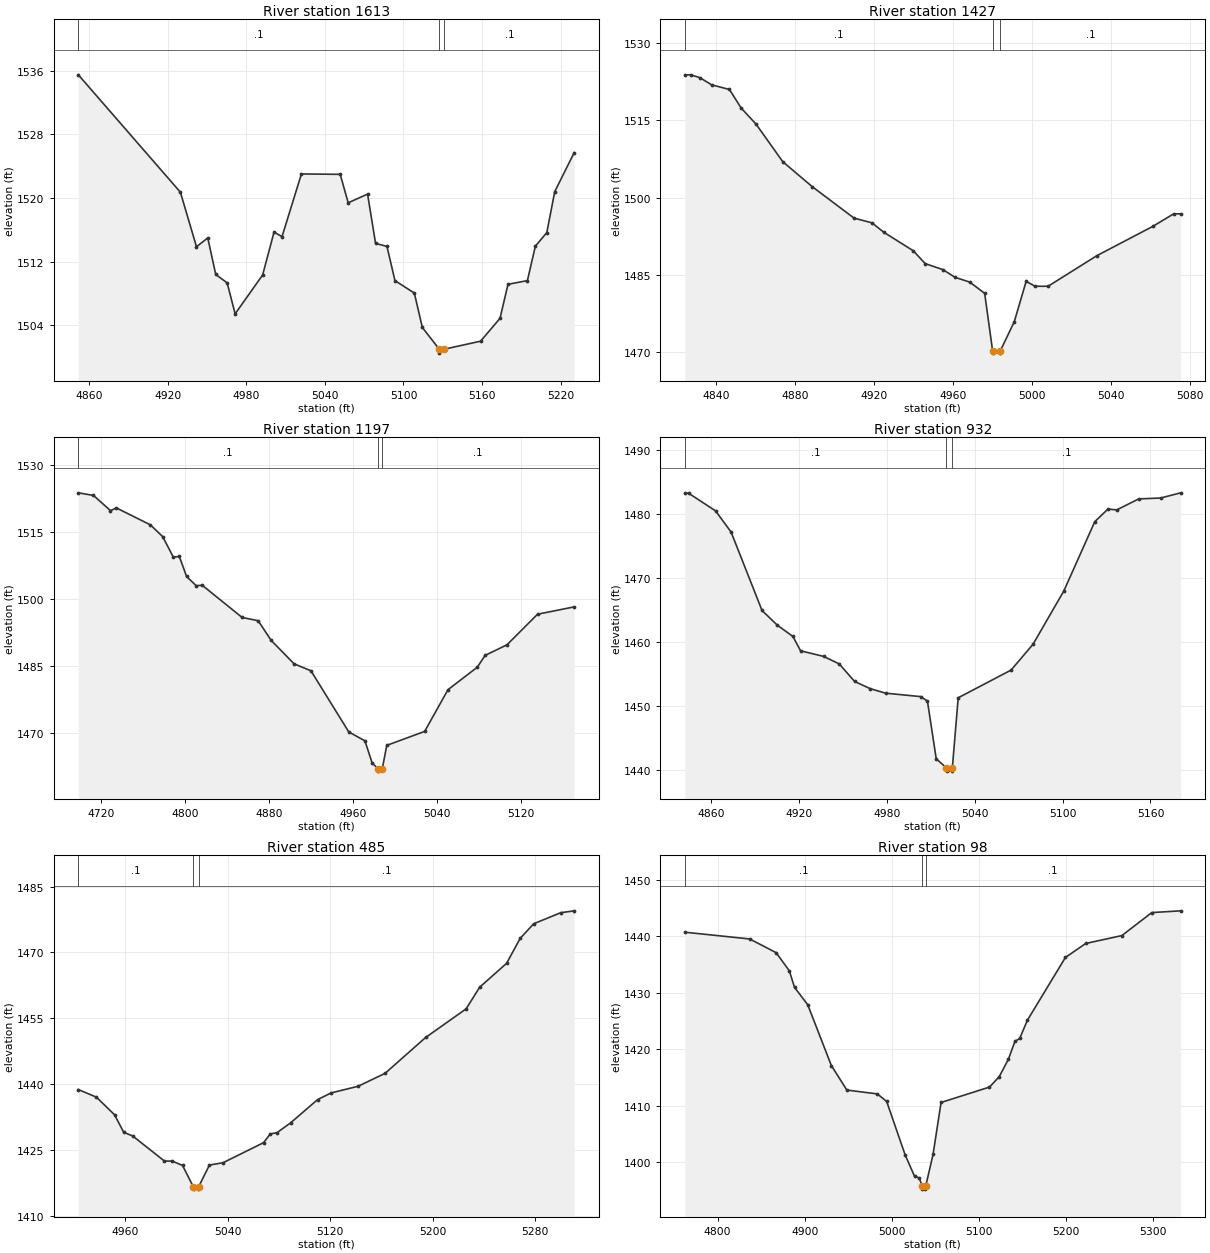
Type RM Length L Ch R = 1 ,1613    ,186,186,186
BEGIN DESCRIPTION:
Stream0012 5.0
END DESCRIPTION:
XS GIS Cut Line= 2
      1999221.22     13893221.72      1999530.91     13893439.34
#Sta/Elev= 30
  4851.8 1535.46  4929.7 1520.73    4942 1513.88  4950.6 1514.99  4956.7  1510.4
  4965.4 1509.35  4971.5 1505.46  4992.5 1510.34  5001.2 1515.72  5007.3 1515.15
  5022.1 1523.02  5051.7 1522.97  5057.8  1519.4  5072.6 1520.49  5078.7 1514.31
  5087.4 1513.92  5093.5 1509.63  5108.3 1508.07  5114.4 1503.75  5127.3 1501.03
  5127.5 1500.53  5131.3 1501.03  5158.9 1502.03  5173.7  1504.9  5179.8 1509.17
  5194.6 1509.63  5200.7 1513.96  5209.4 1515.65  5215.5 1520.81  5230.3 1525.69
#Mann= 3 ,-1 , 0
  4851.8      .1       0  5127.3     .05       0  5131.3      .1       0
Bank Sta=5127.3,5131.3
XS Rating Curve= 0 ,0
Exp/Cntr=0.3,0.1

Type RM Length L Ch R = 1 ,1427    ,230,230,230
BEGIN DESCRIPTION:
Stream0012 3.0
END DESCRIPTION:
XS GIS Cut Line= 3
      1999124.97     13893374.98        1999275.       13893475.
      1999324.98     13893524.98
#Sta/Elev= 30
  4824.1  1523.8  4827.1  1523.8  4831.7 1523.26  4837.7 1521.86  4846.7 1520.96
  4852.7 1517.33  4860.2 1514.23  4873.7 1506.96  4888.7  1502.1  4909.8 1496.02
  4918.8 1495.12  4924.8  1493.3  4939.8 1489.69  4945.8 1487.21  4954.8 1486.04
  4960.9 1484.55  4968.4 1483.62  4975.9 1481.45  4979.9 1470.36  4980.1 1469.86
  4983.6 1469.86  4983.9 1470.36  4990.9 1475.96  4996.9 1483.77  5001.4 1482.82
    5008 1482.82  5032.7 1488.75    5061 1494.42  5071.6 1496.86  5075.1 1496.86
#Mann= 3 ,-1 , 0
  4824.1      .1       0  4979.9     .05       0  4983.9      .1       0
Bank Sta=4979.9,4983.9
XS Rating Curve= 0 ,0
Exp/Cntr=0.3,0.1

Type RM Length L Ch R = 1 ,1197    ,265,265,265
BEGIN DESCRIPTION:
Stream0012 6.0
END DESCRIPTION:
XS GIS Cut Line= 3
      1998954.66     13893384.44       1999078.1     13893611.67
      1999248.73     13893740.34
#Sta/Elev= 30
  4698.4 1523.73  4712.8 1523.15    4729 1519.75  4734.7 1520.34    4767 1516.56
  4778.7 1513.93  4788.9 1509.32  4794.6 1509.48  4801.5 1504.99  4810.7 1502.92
  4816.4 1503.03  4854.4 1495.81  4869.7 1495.08    4882  1490.7  4903.9 1485.42
    4920 1483.86    4956 1470.16  4971.4 1468.17  4978.2 1463.26  4983.9 1461.88
  4984.2 1461.38  4987.9 1461.88  4992.2 1467.15  5028.3 1470.28  5050.5 1479.62
  5078.4 1484.66  5085.9 1487.31  5106.7 1489.68  5135.8 1496.53  5170.7 1498.18
#Mann= 3 ,-1 , 0
  4698.4      .1       0  4983.9     .05       0  4987.9      .1       0
Bank Sta=4983.9,4987.9
XS Rating Curve= 0 ,0
Exp/Cntr=0.3,0.1

Type RM Length L Ch R = 1 ,932     ,447,447,447
BEGIN DESCRIPTION:
Stream0012 2.0
END DESCRIPTION:
XS GIS Cut Line= 3
      1998875.01     13893675.03        1998925.       13893825.
      1999075.04     13893925.02
#Sta/Elev= 30
  4842.2 1483.22  4844.8 1483.22  4863.2 1480.46  4873.8 1477.15  4894.9  1464.9
  4905.4 1462.59    4916 1460.84  4921.2  1458.6    4937 1457.72  4947.6 1456.55
  4958.1 1453.81  4968.7 1452.69  4979.2 1451.98  5003.3 1451.44  5007.8 1450.74
  5013.8 1441.73  5020.8  1440.3  5021.1  1439.8  5024.6  1439.8  5024.8  1440.3
  5028.8 1451.26  5064.9 1455.59  5079.9 1459.63  5100.9 1467.95    5122 1478.77
    5131 1480.74    5137 1480.61    5152 1482.33    5167 1482.47  5180.6 1483.28
#Mann= 3 ,-1 , 0
  4842.2      .1       0  5020.8     .05       0  5024.8      .1       0
Bank Sta=5020.8,5024.8
XS Rating Curve= 0 ,0
Exp/Cntr=0.3,0.1

Type RM Length L Ch R = 1 ,485     ,387,387,387
BEGIN DESCRIPTION:
Stream0012 1.0
END DESCRIPTION:
XS GIS Cut Line= 3
        1998725.       13894175.        1998775.       13894225.
      1999074.96     13894125.01
#Sta/Elev= 30
  4923.5 1438.73  4937.6    1437  4951.8 1432.97  4958.9 1428.99  4965.9 1428.15
  4990.7 1422.42  4996.8 1422.42  5004.8 1421.42  5013.3 1416.52  5013.5 1416.02
    5017 1416.02  5017.3 1416.52  5025.8 1421.51  5036.4 1422.04    5068 1426.61
  5073.3 1428.61  5078.5  1428.9  5089.1 1431.13  5110.2 1436.44  5120.7 1437.96
  5141.8 1439.48  5162.9 1442.44  5194.5 1450.61  5226.1 1457.14  5236.7 1462.09
  5257.7 1467.53  5268.3 1473.23  5278.8 1476.55  5299.9 1479.07  5310.4  1479.5
#Mann= 3 ,-1 , 0
  4923.5      .1       0  5013.3     .05       0  5017.3      .1       0
Bank Sta=5013.3,5017.3
XS Rating Curve= 0 ,0
Exp/Cntr=0.3,0.1

Type RM Length L Ch R = 1 ,98      ,0,0,0
BEGIN DESCRIPTION:
Stream0012 4.0
END DESCRIPTION:
XS GIS Cut Line= 4
      1998561.84     13894414.04      1998662.87     13894571.19
      1998783.51     13894616.08       1999016.4     13894515.07
#Sta/Elev= 30
  4762.3 1440.75  4836.8 1439.55  4867.2 1437.12  4882.3 1433.91  4888.3 1430.97
  4903.5 1427.87  4930.6  1417.1  4948.4 1412.75  4983.4 1412.07  4994.1 1410.74
  5015.4 1401.23  5026.1 1397.47  5031.6 1397.16  5034.9 1395.68  5035.2 1395.18
  5038.7 1395.18  5038.9 1395.68  5047.4 1401.33  5056.6 1410.55  5112.2 1413.28
  5123.4 1415.12    5134 1418.25  5141.4 1421.37  5146.9 1421.91  5155.8 1425.15
  5199.4 1436.27  5222.7 1438.75  5264.2 1440.15  5298.6 1444.23  5331.7 1444.54
#Mann= 3 ,-1 , 0
  4762.3      .1       0  5034.9     .05       0  5038.9      .1       0
Bank Sta=5034.9,5038.9
XS Rating Curve= 0 ,0
Exp/Cntr=0.3,0.1

Chan Stop Cuts=-1
Use User Specified Reach Order=0
Composite Channel Slope=5