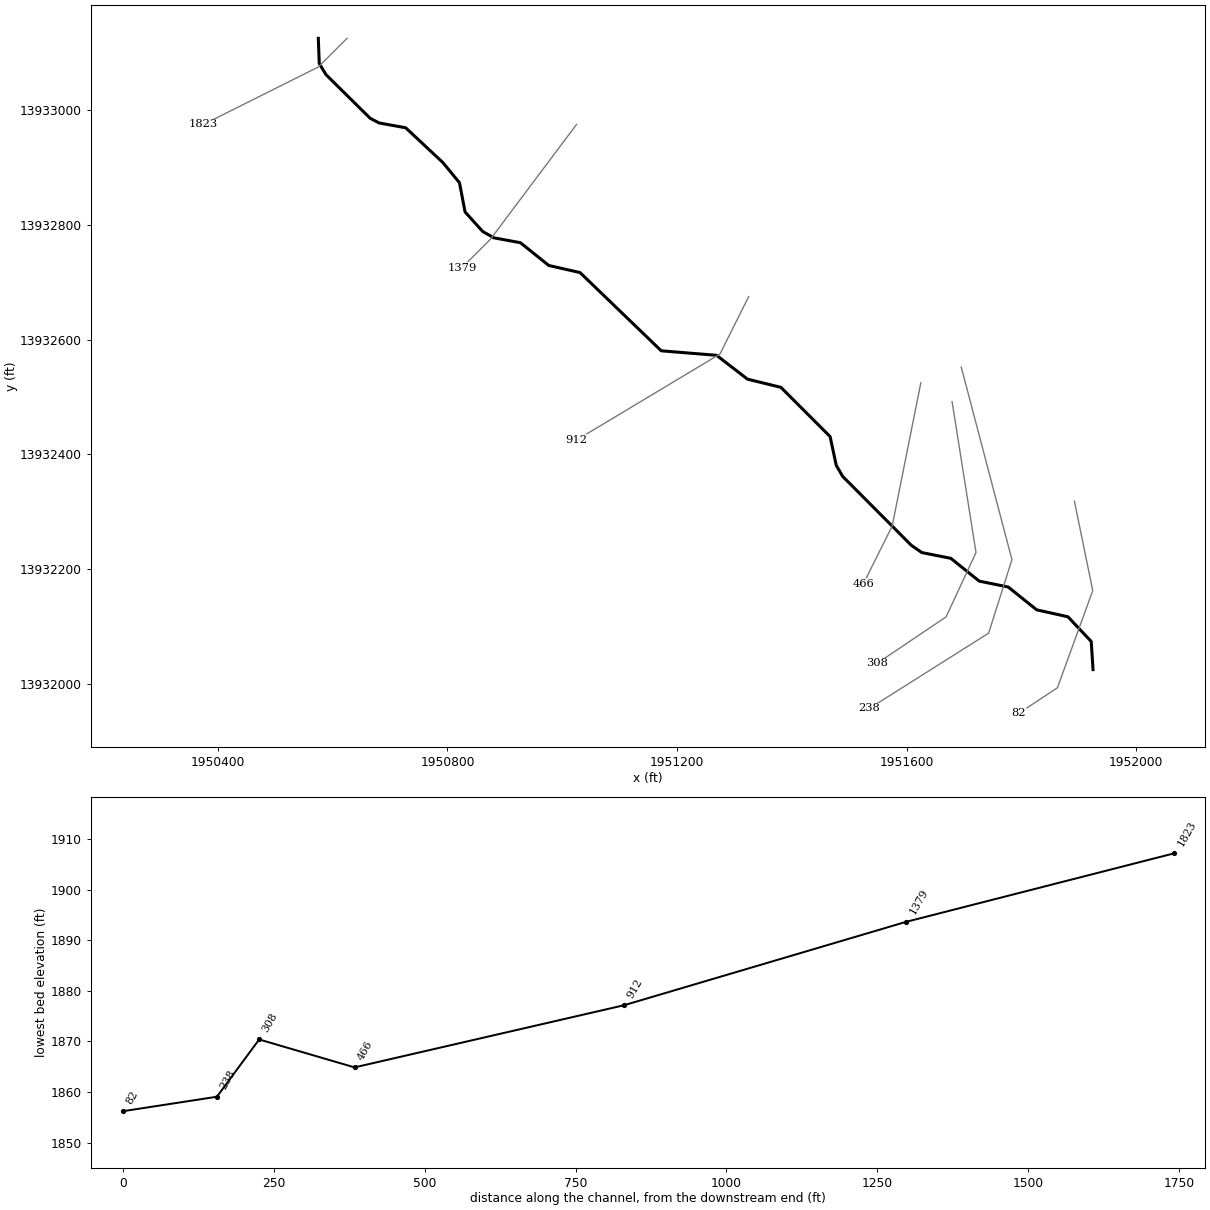
--- Stream0013.prj (project) ---

Proj Title=Stream0013 Base Level Engineering
Current Plan=p01
Default Exp/Contr=0.3,0.1
English Units
Geom File=g01
Flow File=f01
Plan File=p01
Y Axis Title=Elevation
X Axis Title(PF)=Main Channel Distance
X Axis Title(XS)=Station
BEGIN DESCRIPTION:
Stream0013
END DESCRIPTION:
DSS Export Rating Curves= 0
DSS Export Rating Curve Sorted= 0
DSS Export Volume Flow Curves= 0
DXF OffsetX= 0
DXF OffsetY= 0
DXF ScaleX= 1
DXF ScaleY= 10

--- Stream0013.p01 (plan) ---

Plan Title=Multiple Run
Short Identifier=Multiple
Geom File=g01
Flow File=f01
Subcritical Flow
K Sum by GR= 0
Std Step Tol= 0.01
Critical Tol= 0.01
Num of Std Step Trials= 20
Max Error Tol= 0.3
Flow Tol Ratio= 0.001
Split Flow NTrial= 30
Split Flow Tol= 0.02
Split Flow Ratio= 0.02
Log Output Level= 0
Friction Slope Method= 1
Unsteady Friction Slope Method= 2
Unsteady Bridges Friction Slope Method= 1
Parabolic Critical Depth
Global Vel Dist=  1 , 1 , 1
Global Log Level= 0
CheckData=True
Encroach Param= -1, 0, 0, 0
BEGIN DESCRIPTION:
Multiple Run
END DESCRIPTION:

--- Stream0013.f01 (steady flow) ---

Flow Title=Multiple
Number of Profiles=7
Profile Names=10-year,25-year,50-year,1pct_min,100-year,1pct_plu,500-year
River Rch & RM= Stream0013,Reach-1,1823
     367     579     766     493     984    1963    1595
Boundary for River Rch & Prof#=Stream0013,Reach-1,1
Up Type=0
Dn Type=3
Dn Slope=0.005
Boundary for River Rch & Prof#=Stream0013,Reach-1,2
Up Type=0
Dn Type=3
Dn Slope=0.005
Boundary for River Rch & Prof#=Stream0013,Reach-1,3
Up Type=0
Dn Type=3
Dn Slope=0.005
Boundary for River Rch & Prof#=Stream0013,Reach-1,4
Up Type=0
Dn Type=3
Dn Slope=0.005
Boundary for River Rch & Prof#=Stream0013,Reach-1,5
Up Type=0
Dn Type=3
Dn Slope=0.005
Boundary for River Rch & Prof#=Stream0013,Reach-1,6
Up Type=0
Dn Type=3
Dn Slope=0.005
Boundary for River Rch & Prof#=Stream0013,Reach-1,7
Up Type=0
Dn Type=3
Dn Slope=0.005

--- Stream0013.g01 (geometry) ---

Geom Title=Existing Conditions
Program Version=4.10

River Reach=Stream0013      ,Reach-1
Reach XY= 30
        1950575.       13933125.      1950576.67     13933081.13
      1950588.46     13933061.69       1950665.3     13932985.76
      1950681.04     13932977.53       1950727.3     13932969.15
      1950792.08     13932908.57      1950821.02     13932873.34
      1950830.75     13932822.46      1950861.43     13932788.47
      1950880.85     13932777.42      1950927.16     13932768.89
      1950976.73     13932729.19      1951031.06     13932716.86
      1951172.57     13932580.52      1951269.03     13932572.67
      1951322.83     13932531.14      1951381.07     13932516.87
      1951466.85     13932431.07      1951477.54     13932381.05
      1951488.63     13932361.79      1951608.32     13932241.64
      1951626.63     13932228.95      1951677.19      13932218.9
      1951726.72     13932179.16       1951777.2     13932168.92
      1951826.75     13932129.17      1951881.31     13932117.04
      1951921.86     13932073.97        1951925.       13932025.

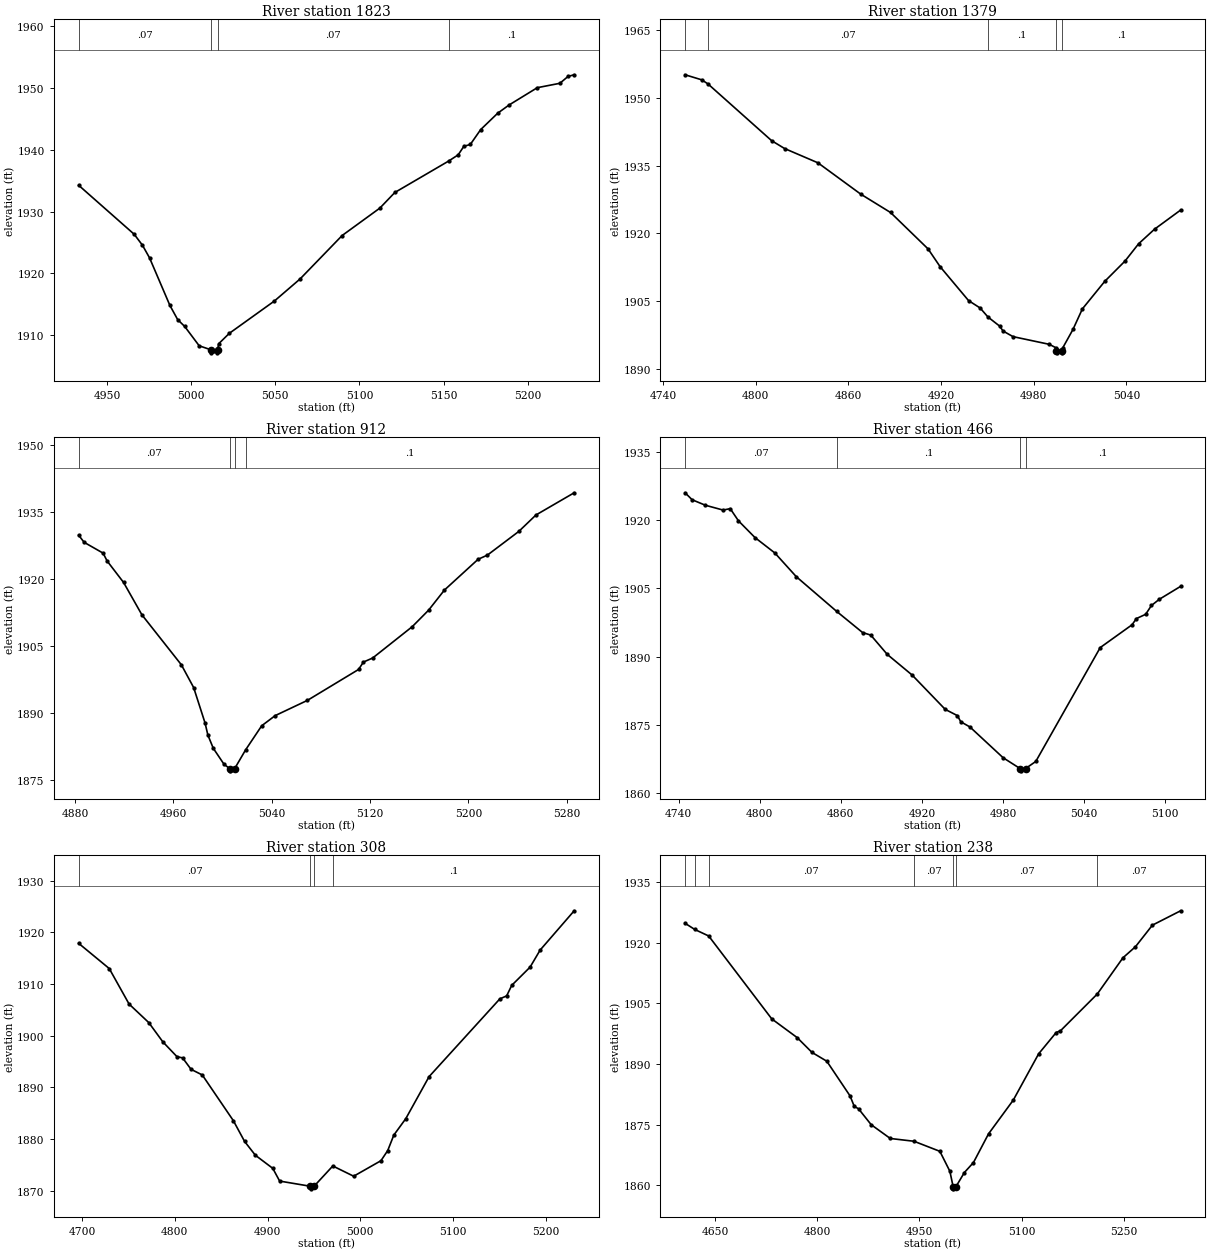
Type RM Length L Ch R = 1 ,1823    ,444,444,444
BEGIN DESCRIPTION:
Stream0013 4.0
END DESCRIPTION:
XS GIS Cut Line= 3
      1950625.02     13933125.02        1950575.       13933075.
      1950375.04     13932975.02
#Sta/Elev= 30
  4933.2 1934.27  4966.2 1926.33  4971.1 1924.56  4975.3 1922.52  4987.4 1914.81
    4992 1912.52  4996.2  1911.4  5004.8 1908.27  5011.7 1907.63    5012 1907.13
  5015.5 1907.13  5015.7 1907.63  5016.4 1908.61  5022.7 1910.29  5049.5 1915.53
  5064.7 1919.09  5089.7 1926.13  5112.1 1930.57    5121  1933.1  5152.9 1938.18
  5158.6 1939.19    5162 1940.58  5165.8 1940.87    5172 1943.29  5182.1 1945.94
  5188.8 1947.26  5205.6 1950.07    5219 1950.78  5223.9  1951.9  5227.5 1952.16
#Mann= 4 ,-1 , 0
  4933.2     .07       0  5011.7     .05       0  5015.7     .07       0
  5152.9      .1       0
Bank Sta=5011.7,5015.7
XS Rating Curve= 0 ,0
Exp/Cntr=0.3,0.1

Type RM Length L Ch R = 1 ,1379    ,467,467,467
BEGIN DESCRIPTION:
Stream0013 3.0
END DESCRIPTION:
XS GIS Cut Line= 3
      1951025.03     13932975.03        1950875.       13932775.
      1950824.97     13932724.97
#Sta/Elev= 30
  4754.3 1955.06  4765.1 1953.94  4769.1 1953.04  4810.3  1940.5  4818.7 1938.76
  4840.3  1935.6    4868 1928.68  4887.3 1924.62  4911.6 1916.57  4919.4 1912.64
  4937.8 1905.15  4945.3 1903.51  4950.4 1901.51    4958 1899.49  4960.1 1898.43
  4966.6 1897.18  4990.1 1895.48  4994.1 1894.77  4994.6  1894.1  4994.8  1893.6
  4998.3  1893.6  4998.6  1894.1  4998.7 1894.65  5005.4 1898.77  5011.5 1903.32
    5026 1909.41  5039.1 1913.89  5047.9 1917.71  5058.2 1920.93  5075.1 1925.16
#Mann= 5 ,-1 , 0
  4754.3      .1       0  4769.1     .07       0  4950.4      .1       0
  4994.6     .05       0  4998.6      .1       0
Bank Sta=4994.6,4998.6
XS Rating Curve= 0 ,0
Exp/Cntr=0.3,0.1

Type RM Length L Ch R = 1 ,912     ,446,446,446
BEGIN DESCRIPTION:
Stream0013 2.0
END DESCRIPTION:
XS GIS Cut Line= 3
      1951324.99     13932674.98        1951275.       13932575.
      1951025.03     13932425.02
#Sta/Elev= 30
  4882.8 1929.78  4887.3 1928.18  4902.7 1925.77    4906 1924.01  4919.4 1919.21
  4934.3 1911.99  4966.4 1900.83  4976.4 1895.75  4985.7 1887.82    4988 1885.12
  4992.4 1882.17  5001.2 1878.58  5005.8 1877.64    5006 1877.14  5009.8 1877.64
  5018.7 1881.83  5031.8 1887.21  5042.8 1889.48    5069 1892.88  5110.6 1899.78
  5114.6 1901.44  5122.1 1902.34  5154.3 1909.34  5167.6 1913.02  5180.5 1917.52
  5207.9 1924.39  5215.5 1925.33    5241 1930.61    5255 1934.29  5286.1 1939.25
#Mann= 4 ,-1 , 0
  4882.8     .07       0  5005.8     .05       0  5009.8     .07       0
  5018.7      .1       0
Bank Sta=5005.8,5009.8
XS Rating Curve= 0 ,0
Exp/Cntr=0.3,0.1

Type RM Length L Ch R = 1 ,466     ,158,158,158
BEGIN DESCRIPTION:
Stream0013 1.0
END DESCRIPTION:
XS GIS Cut Line= 3
      1951624.99     13932524.97        1951575.       13932275.
      1951525.01     13932175.02
#Sta/Elev= 30
  4744.8 1926.01    4750 1924.48  4759.8 1923.27  4772.9 1922.21  4778.2 1922.52
  4784.3 1919.84  4796.5 1916.17  4811.2 1912.78  4827.1 1907.56  4856.9 1899.95
  4876.1 1895.29  4882.2 1894.72  4894.4 1890.48  4912.8 1885.94  4937.3 1878.39
  4946.3 1877.02  4948.8 1875.67  4955.6 1874.52  4980.1 1867.77  4992.7 1865.38
    4993 1864.88  4996.7 1865.38  5004.3 1866.94    5052 1891.98  5075.5 1896.98
  5078.8 1898.36  5085.6 1899.29  5089.9 1901.23  5095.6 1902.57  5111.5 1905.44
#Mann= 4 ,-1 , 0
  4744.8     .07       0  4856.9      .1       0  4992.7     .05       0
  4996.7      .1       0
Bank Sta=4992.7,4996.7
XS Rating Curve= 0 ,0
Exp/Cntr=0.3,0.1

Type RM Length L Ch R = 1 ,308     ,70,70,70
BEGIN DESCRIPTION:
Stream0013 0.1
END DESCRIPTION:
XS GIS Cut Line= 4
      1951679.41     13932491.94      1951721.08      13932228.9
        1951669.     13932116.92      1951549.26     13932036.23
#Sta/Elev= 30
  4696.3 1917.87  4729.3 1912.99  4750.7 1906.12  4771.9 1902.54  4787.1 1898.81
  4802.3 1895.95  4808.4 1895.71  4817.5  1893.5  4829.6 1892.41  4863.1 1883.57
  4875.2 1879.56  4886.8 1876.89  4905.6 1874.35    4913 1871.89  4946.1 1870.89
  4946.4 1870.39  4950.1 1870.89  4970.3 1874.81  4992.8 1872.83  5022.2 1875.83
  5029.5 1877.79  5036.1 1880.79    5049 1883.97  5074.1 1892.09  5150.4 1907.13
  5157.7  1907.7  5163.2 1909.74    5183 1913.27  5193.8 1916.56  5230.5 1924.16
#Mann= 4 ,-1 , 0
  4696.3     .07       0  4946.1     .05       0  4950.1     .07       0
  4970.3      .1       0
Bank Sta=4946.1,4950.1
XS Rating Curve= 0 ,0
Exp/Cntr=0.3,0.1

Type RM Length L Ch R = 1 ,238     ,156,156,156
BEGIN DESCRIPTION:
Stream0013 0.0
END DESCRIPTION:
XS GIS Cut Line= 4
      1951695.36     13932552.18      1951783.67     13932216.63
      1951743.11     13932088.56      1951535.66     13931957.51
#Sta/Elev= 30
  4606.3 1924.83  4620.5  1923.3  4640.9 1921.69  4733.4 1901.16  4770.7 1896.52
  4792.4 1892.86  4814.1 1890.68  4848.2 1882.09  4854.4 1879.49  4860.6 1878.91
  4879.2 1874.96  4907.2 1871.55    4942 1870.86  4979.9 1868.37  4994.6 1863.43
  4999.4 1859.58  4999.7 1859.08  5003.4 1859.58  5015.8 1863.11  5029.2  1865.6
  5051.3  1872.7  5087.6 1881.06  5124.8 1892.52  5150.5 1897.79  5156.8 1898.22
  5210.8 1907.33  5248.4 1916.29  5266.8 1919.04  5291.6 1924.37    5333 1927.93
#Mann= 7 ,-1 , 0
  4606.3     .07       0  4620.5    .035       0  4640.9     .07       0
    4942     .07       0  4999.4     .05       0  5003.4     .07       0
  5210.8     .07       0
Bank Sta=4999.4,5003.4
XS Rating Curve= 0 ,0
Exp/Cntr=0.3,0.1

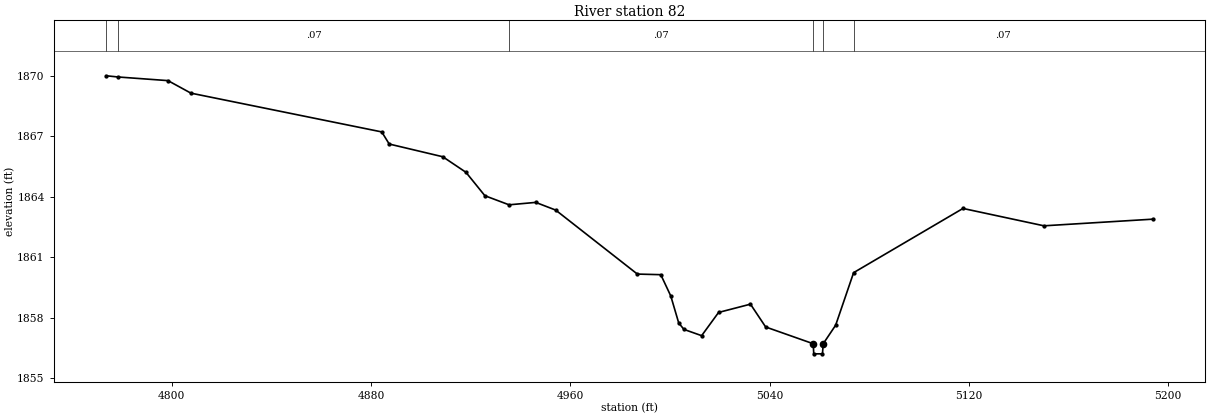
Type RM Length L Ch R = 1 ,82      ,0,0,0
BEGIN DESCRIPTION:
Stream0013 0.5
END DESCRIPTION:
XS GIS Cut Line= 4
      1951892.56     13932318.56      1951924.52     13932162.63
      1951862.91     13931993.28      1951795.48     13931948.72
#Sta/Elev= 30
  4773.7 1869.99  4778.5 1869.93  4798.5 1869.75  4807.7 1869.13  4884.3 1867.21
  4887.3 1866.61  4908.8 1865.98  4918.1 1865.21  4925.7 1864.05  4935.4  1863.6
  4946.1 1863.72  4954.1 1863.34  4986.9 1860.17  4996.3 1860.14  5000.3 1859.09
  5003.5 1857.75  5005.6 1857.43  5012.7 1857.12  5019.5 1858.27  5032.3 1858.68
  5038.4 1857.55  5057.5 1856.72  5057.7 1856.22  5061.2 1856.22  5061.5 1856.72
  5066.5 1857.64  5073.7 1860.24  5117.6 1863.42  5150.1 1862.56  5193.9 1862.89
#Mann= 6 ,-1 , 0
  4773.7      .1       0  4778.5     .07       0  4935.4     .07       0
  5057.5     .05       0  5061.5     .07       0  5073.7     .07       0
Bank Sta=5057.5,5061.5
XS Rating Curve= 0 ,0
Exp/Cntr=0.3,0.1

Chan Stop Cuts=-1
Use User Specified Reach Order=0
Composite Channel Slope=5