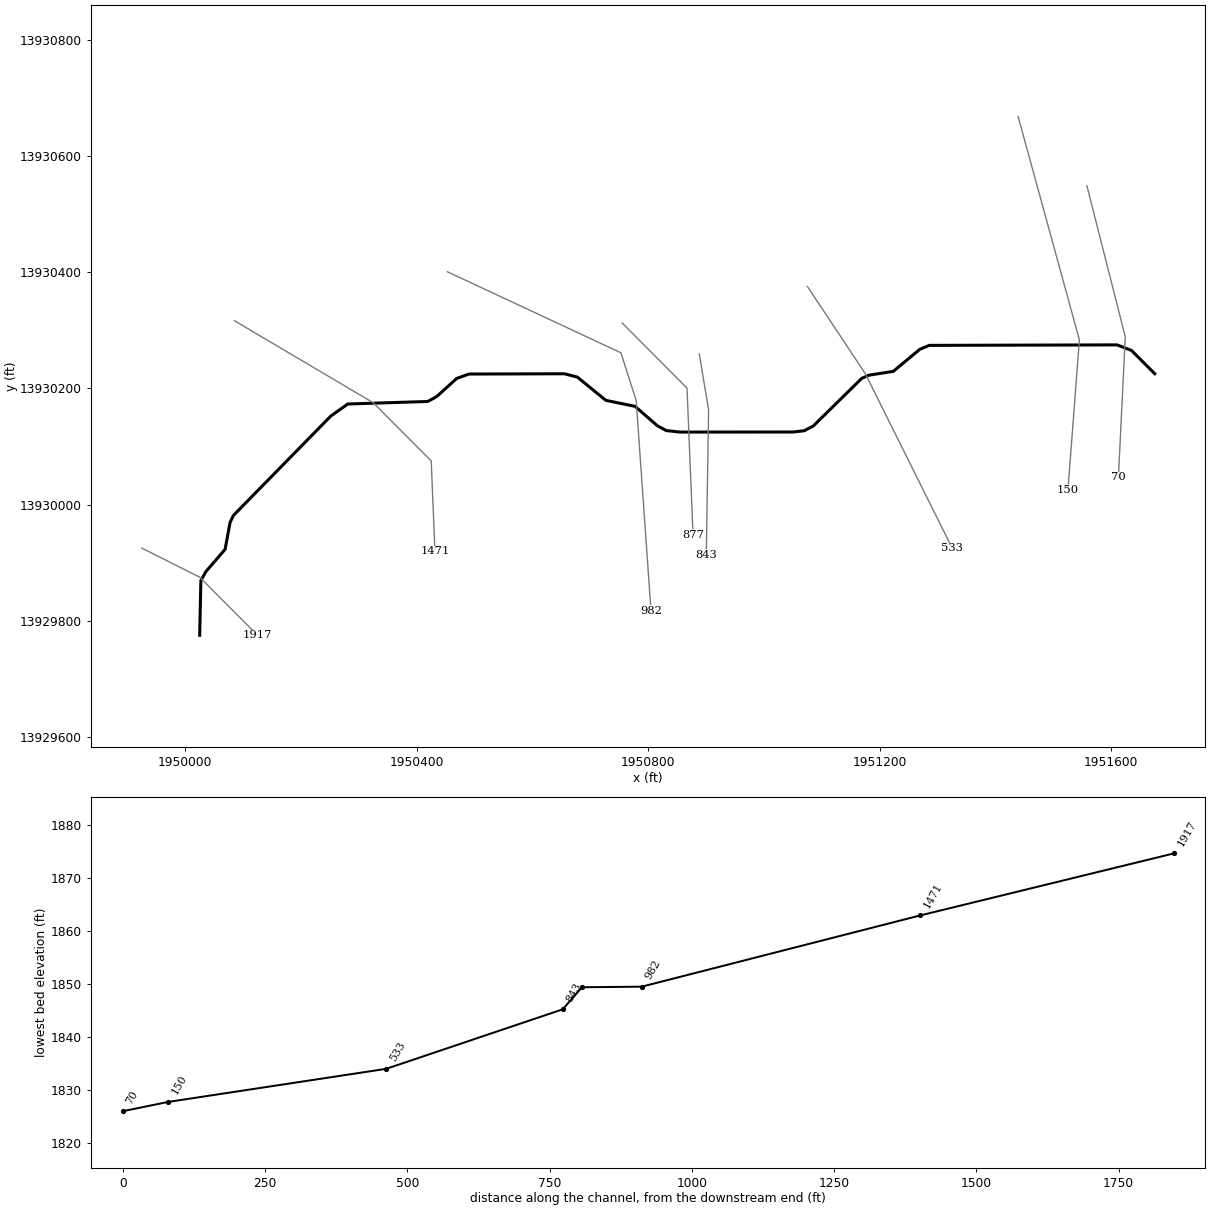
--- Stream0014.prj (project) ---

Proj Title=Stream0014 Base Level Engineering
Current Plan=p01
Default Exp/Contr=0.3,0.1
English Units
Geom File=g01
Flow File=f01
Plan File=p01
BEGIN DESCRIPTION:
Stream0014
END DESCRIPTION:

--- Stream0014.p01 (plan) ---

Plan Title=Multiple Run
Short Identifier=Multiple
Geom File=g01
Flow File=f01
Subcritical Flow
K Sum by GR= 0
Std Step Tol= 0.01
Critical Tol= 0.01
Num of Std Step Trials= 20
Max Error Tol= 0.3
Flow Tol Ratio= 0.001
Split Flow NTrial= 30
Split Flow Tol= 0.02
Split Flow Ratio= 0.02
Log Output Level= 0
Friction Slope Method= 1
Unsteady Friction Slope Method= 2
Unsteady Bridges Friction Slope Method= 1
Parabolic Critical Depth
Global Vel Dist=  1 , 1 , 1
Global Log Level= 0
CheckData=True
Encroach Param= -1, 0, 0, 0
BEGIN DESCRIPTION:
Multiple Run
END DESCRIPTION:

--- Stream0014.f01 (steady flow) ---

Flow Title=Multiple
Number of Profiles=7
Profile Names=10-year,25-year,50-year,1pct_min,100-year,1pct_plu,500-year
River Rch & RM= Stream0014,Reach-1,1917
     561     914    1238     815    1626    3244    2755
River Rch & RM= Stream0014,Reach-1,533
     903    1519    2099    1406    2805    5597    4936
Boundary for River Rch & Prof#=Stream0014,Reach-1,1
Up Type=0
Dn Type=3
Dn Slope=0.005
Boundary for River Rch & Prof#=Stream0014,Reach-1,2
Up Type=0
Dn Type=3
Dn Slope=0.005
Boundary for River Rch & Prof#=Stream0014,Reach-1,3
Up Type=0
Dn Type=3
Dn Slope=0.005
Boundary for River Rch & Prof#=Stream0014,Reach-1,4
Up Type=0
Dn Type=3
Dn Slope=0.005
Boundary for River Rch & Prof#=Stream0014,Reach-1,5
Up Type=0
Dn Type=3
Dn Slope=0.005
Boundary for River Rch & Prof#=Stream0014,Reach-1,6
Up Type=0
Dn Type=3
Dn Slope=0.005
Boundary for River Rch & Prof#=Stream0014,Reach-1,7
Up Type=0
Dn Type=3
Dn Slope=0.005

--- Stream0014.g01 (geometry) ---

Geom Title=Existing Conditions

River Reach=Stream0014,Reach-1
Reach XY= 30
      1950025.00     13929775.00      1950027.07     13929869.14
      1950035.79     13929884.67      1950068.89     13929922.82
      1950077.49     13929968.97      1950083.14     13929981.06
      1950251.47     13930152.14      1950280.86     13930172.93
      1950419.06     13930177.27      1950434.64     13930185.86
      1950468.94     13930216.86      1950490.22     13930224.48
      1950654.97     13930224.94      1950677.35     13930219.29
      1950726.74     13930179.19      1950777.18     13930168.88
      1950815.33     13930135.80      1950830.93     13930127.24
      1950854.85     13930124.64      1951050.10     13930124.76
      1951069.22     13930126.89      1951084.98     13930135.05
      1951168.85     13930217.09      1951181.04     13930222.49
      1951223.31     13930229.08      1951268.92     13930266.92
      1951285.49     13930273.81      1951609.85     13930274.64
      1951634.98     13930264.95      1951675.00     13930225.00

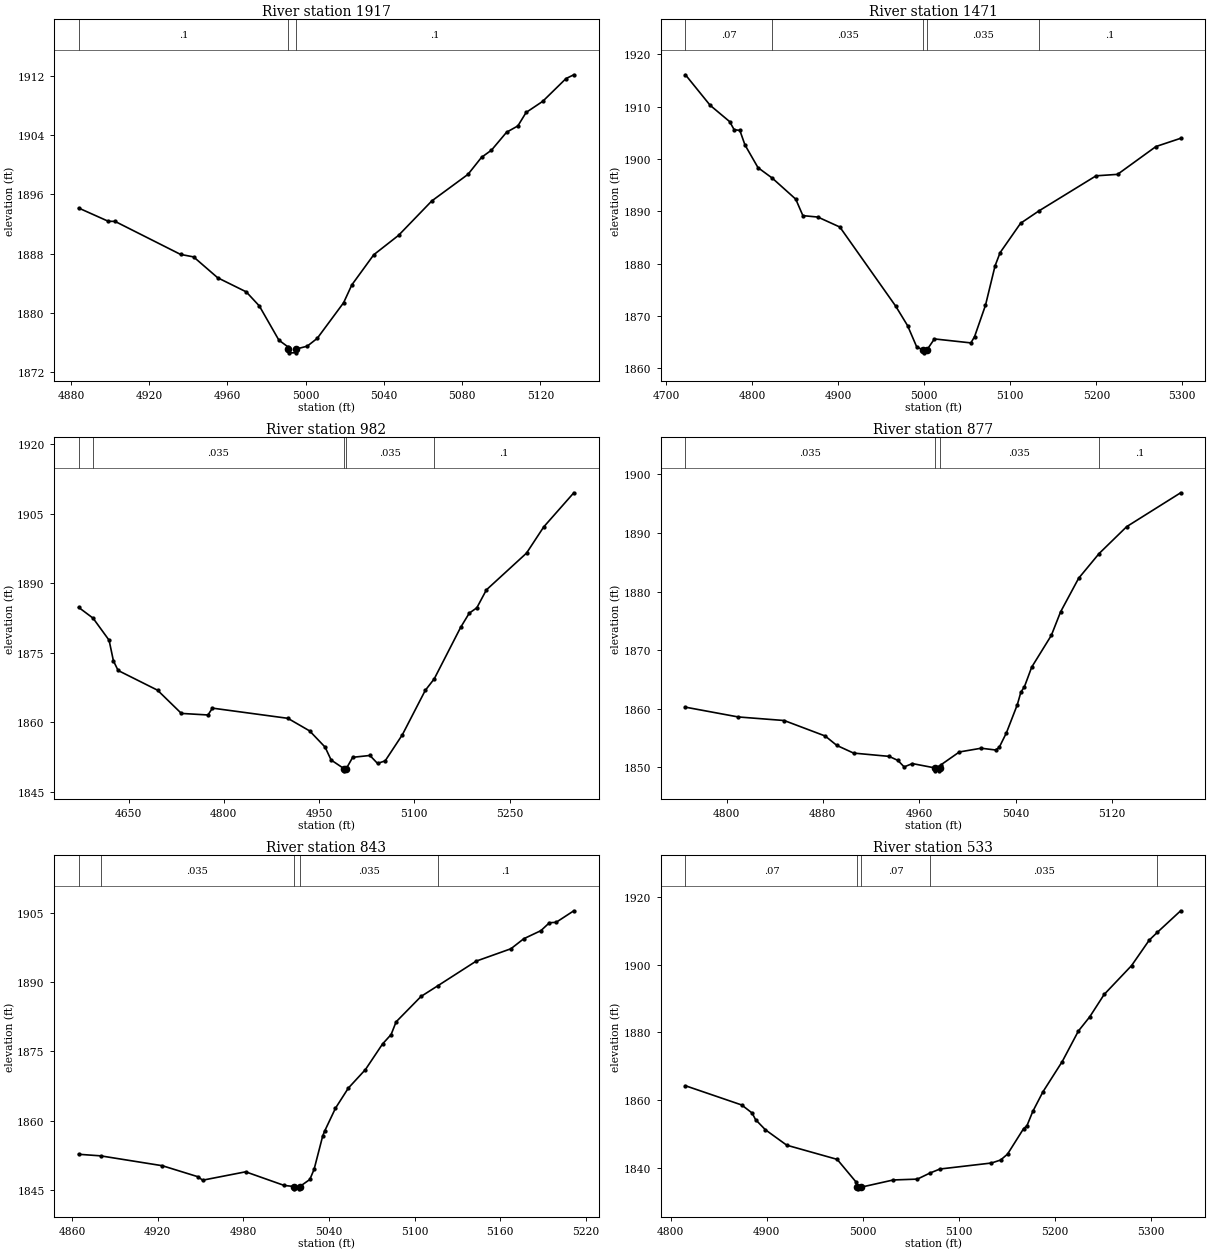
Type RM Length L Ch R = 1,1917,446,446,446
BEGIN DESCRIPTION:
Stream0014 4.0
END DESCRIPTION:
XS GIS Cut Line= 3
      1949925.04     13929924.98      1950025.00     13929875.00
      1950125.02     13929774.98
#Sta/Elev= 30
  4883.9 1894.16  4899.1 1892.37  4902.5 1892.36  4936.0 1887.91  4942.7 1887.57
  4955.0 1884.76  4969.6 1882.86  4976.3 1880.96  4986.3 1876.35  4990.8 1875.47
  4991.0 1875.14  4991.3 1874.64  4994.8 1874.64  4995.0 1875.14  5000.8 1875.54
  5005.9 1876.59  5019.4 1881.40  5023.6 1883.80  5034.8 1887.86  5047.5 1890.48
  5064.5 1895.12  5083.0 1898.70  5089.9 1900.99  5095.0 1901.96  5102.7 1904.37
  5108.5 1905.23  5112.7 1907.04  5121.2 1908.54  5133.1 1911.61  5137.1 1912.12
#Mann=3,-1,0
  4883.9     0.1       0  4991.0    0.05       0  4995.0     0.1       0
Bank Sta=4991,4995
Exp/Cntr=0.3,0.1

Type RM Length L Ch R = 1,1471,489,489,489
BEGIN DESCRIPTION:
Stream0014 3.0
END DESCRIPTION:
XS GIS Cut Line= 4
      1950084.90     13930316.32      1950325.00     13930175.00
      1950425.00     13930075.00      1950431.44     13929919.16
#Sta/Elev= 30
  4722.1 1916.07  4750.8 1910.24  4773.5 1907.12  4778.7 1905.59  4785.4 1905.43
  4791.3 1902.67  4806.5 1898.32  4823.1 1896.32  4850.4 1892.30  4858.7 1889.15
  4876.1 1888.88  4901.7 1886.97  4966.7 1871.84  4980.5 1868.12  4991.0 1864.10
  4998.7 1863.43  4999.0 1862.93  5002.7 1863.43  5011.7 1865.59  5054.1 1864.83
  5058.4 1866.03  5071.1 1872.03  5082.2 1879.54  5088.1 1882.08  5111.9 1887.69
  5133.2 1890.05  5199.7 1896.76  5224.7 1897.04  5269.4 1902.36  5298.1 1903.93
#Mann=5,-1,0
  4722.1    0.07       0  4823.1   0.035       0  4998.7   0.035       0
  5002.7   0.035       0  5133.2     0.1       0
Bank Sta=4998.7,5002.7
Exp/Cntr=0.3,0.1

Type RM Length L Ch R = 1,982,105,105,105
BEGIN DESCRIPTION:
Stream0014 2.0
END DESCRIPTION:
XS GIS Cut Line= 4
      1950452.93     13930400.47      1950752.74     13930261.01
      1950779.14     13930178.78      1950804.73     13929816.90
#Sta/Elev= 30
  4571.3 1884.80  4594.1 1882.46  4619.3 1877.70  4626.1 1873.25  4633.5 1871.17
  4695.6 1866.91  4733.1 1861.90  4775.0 1861.56  4782.0 1863.04  4900.8 1860.84
  4935.1 1858.12  4959.5 1854.61  4968.9 1851.84  4988.9 1850.00  4989.1 1849.50
  4992.9 1850.00  5002.9 1852.42  5030.0 1852.82  5042.0 1851.10  5054.0 1851.65
  5081.1 1857.29  5117.2 1866.88  5131.3 1869.36  5172.8 1880.46  5186.4 1883.54
  5198.4 1884.71  5213.4 1888.57  5276.6 1896.51  5303.7 1902.17  5351.1 1909.54
#Mann=5,-1,0
  4571.3    0.07       0  4594.1   0.035       0  4988.9   0.035       0
  4992.9   0.035       0  5131.3     0.1       0
Bank Sta=4988.9,4992.9
Exp/Cntr=0.3,0.1

Type RM Length L Ch R = 1,877,34,34,34
BEGIN DESCRIPTION:
Stream0014 7.0
END DESCRIPTION:
XS GIS Cut Line= 3
      1950754.94     13930312.23      1950866.92     13930200.26
      1950877.33     13929947.63
#Sta/Elev= 30
  4765.9 1860.26  4809.7 1858.59  4847.9 1857.98  4881.9 1855.34  4891.6 1853.73
  4905.5 1852.42  4935.0 1851.86  4942.3 1851.17  4947.5 1850.06  4954.3 1850.63
  4973.0 1849.89  4973.2 1849.39  4976.7 1849.39  4977.0 1849.89  4978.3 1850.45
  4993.3 1852.61  5011.4 1853.25  5023.4 1852.95  5026.4 1853.38  5032.4 1855.87
  5041.5 1860.70  5044.4 1862.81  5047.4 1863.76  5053.4 1867.09  5069.7 1872.51
  5077.4 1876.53  5092.4 1882.27  5109.4 1886.49  5132.3 1891.08  5177.1 1896.86
#Mann=4,-1,0
  4765.9   0.035       0  4973.0   0.035       0  4977.0   0.035       0
  5109.4     0.1       0
Bank Sta=4973,4977
Exp/Cntr=0.3,0.1

Type RM Length L Ch R = 1,843,310,310,310
BEGIN DESCRIPTION:
Mapping XS d0353a8f
END DESCRIPTION:
XS GIS Cut Line= 3
      1950888.14     13930258.98      1950904.20     13930162.85
      1950900.20     13929913.14
#Sta/Elev= 30
  4864.5 1852.71  4879.9 1852.37  4923.2 1850.23  4948.4 1847.82  4951.4 1847.09
  4981.6 1848.91  5008.6 1845.96  5015.6 1845.72  5015.8 1845.22  5019.3 1845.22
  5019.6 1845.72  5026.6 1847.25  5029.6 1849.45  5035.6 1856.63  5036.9 1857.67
  5044.6 1862.70  5053.6 1867.05  5065.6 1871.07  5077.6 1876.62  5083.6 1878.66
  5087.1 1881.41  5104.6 1886.92  5116.3 1889.22  5143.2 1894.56  5167.6 1897.25
  5176.6 1899.42  5188.6 1901.17  5194.6 1902.89  5199.3 1902.98  5211.7 1905.48
#Mann=5,-1,0
  4864.5    0.07       0  4879.9   0.035       0  5015.6   0.035       0
  5019.6   0.035       0  5116.3     0.1       0
Bank Sta=5015.6,5019.6
Exp/Cntr=0.3,0.1

Type RM Length L Ch R = 1,533,383,383,383
BEGIN DESCRIPTION:
Stream0014 1.0
END DESCRIPTION:
XS GIS Cut Line= 3
      1951075.00     13930375.00      1951175.00     13930225.00
      1951325.01     13929924.99
#Sta/Elev= 30
  4815.5 1864.33  4874.1 1858.67  4884.9 1856.31  4888.5 1854.37  4898.7 1851.39
  4921.0 1846.84  4973.5 1842.67  4993.1 1836.03  4994.6 1834.50  4994.9 1834.00
  4998.6 1834.50  5031.9 1836.61  5057.0 1836.86  5070.0 1838.63  5080.5 1839.83
  5134.2 1841.60  5143.7 1842.48  5150.9 1844.21  5167.7 1851.74  5171.1 1852.54
  5177.2 1856.77  5187.8 1862.55  5207.9 1871.46  5224.7 1880.43  5236.5 1884.60
  5251.5 1891.18  5280.1 1899.69  5298.5 1907.18  5307.0 1909.49  5331.2 1915.81
#Mann=5,-1,0
  4815.5    0.07       0  4994.6    0.05       0  4998.6    0.07       0
  5070.0   0.035       0  5307.0     0.1       0
Bank Sta=4994.6,4998.6
Exp/Cntr=0.3,0.1

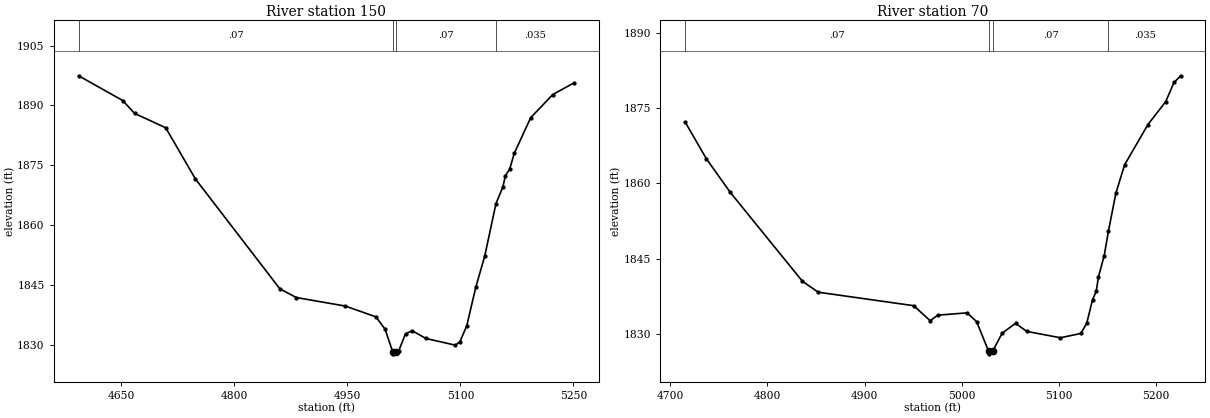
Type RM Length L Ch R = 1,150,80,80,80
BEGIN DESCRIPTION:
Stream0014 0.1
END DESCRIPTION:
XS GIS Cut Line= 3
      1951438.88     13930667.73      1951544.77     13930283.29
      1951525.00     13930025.00
#Sta/Elev= 30
  4593.1 1897.42  4651.7 1891.21  4667.3 1888.00  4708.7 1884.39  4748.2 1871.55
  4860.2 1844.05  4882.0 1841.87  4947.3 1839.72  4987.8 1837.02  4999.9 1833.93
  5010.0 1828.26  5010.2 1827.76  5014.0 1828.26  5018.0 1828.52  5027.0 1832.78
  5036.0 1833.53  5054.1 1831.61  5093.2 1829.93  5099.2 1830.78  5108.3 1834.78
  5120.3 1844.44  5132.3 1852.34  5147.1 1865.41  5156.4 1869.63  5159.4 1872.28
  5165.4 1874.12  5171.4 1878.01  5193.2 1886.93  5222.6 1892.73  5250.9 1895.66
#Mann=4,-1,0
  4593.1    0.07       0  5010.0    0.05       0  5014.0    0.07       0
  5147.1   0.035       0
Bank Sta=5010,5014
Exp/Cntr=0.3,0.1

Type RM Length L Ch R = 1,70,0,0,0
BEGIN DESCRIPTION:
Stream0014 0.0
END DESCRIPTION:
XS GIS Cut Line= 3
      1951557.77     13930548.31      1951624.03     13930288.56
      1951612.19     13930046.62
#Sta/Elev= 30
  4715.2 1872.28  4737.0 1864.98  4761.7 1858.23  4836.0 1840.49  4852.3 1838.30
  4950.6 1835.61  4967.6 1832.61  4975.4 1833.72  5005.6 1834.18  5015.4 1832.43
  5027.8 1826.50  5028.0 1826.00  5031.8 1826.50  5041.7 1830.12  5055.5 1832.09
  5067.0 1830.48  5101.7 1829.21  5122.8 1830.07  5128.8 1832.11  5134.8 1836.81
  5138.6 1838.49  5140.8 1841.30  5146.8 1845.61  5151.2 1850.56  5158.8 1858.06
  5167.8 1863.73  5191.8 1871.76  5210.1 1876.33  5218.7 1880.16  5225.5 1881.50
#Mann=4,-1,0
  4715.2    0.07       0  5027.8    0.05       0  5031.8    0.07       0
  5151.2   0.035       0
Bank Sta=5027.8,5031.8
Exp/Cntr=0.3,0.1

Chan Stop Cuts=-1