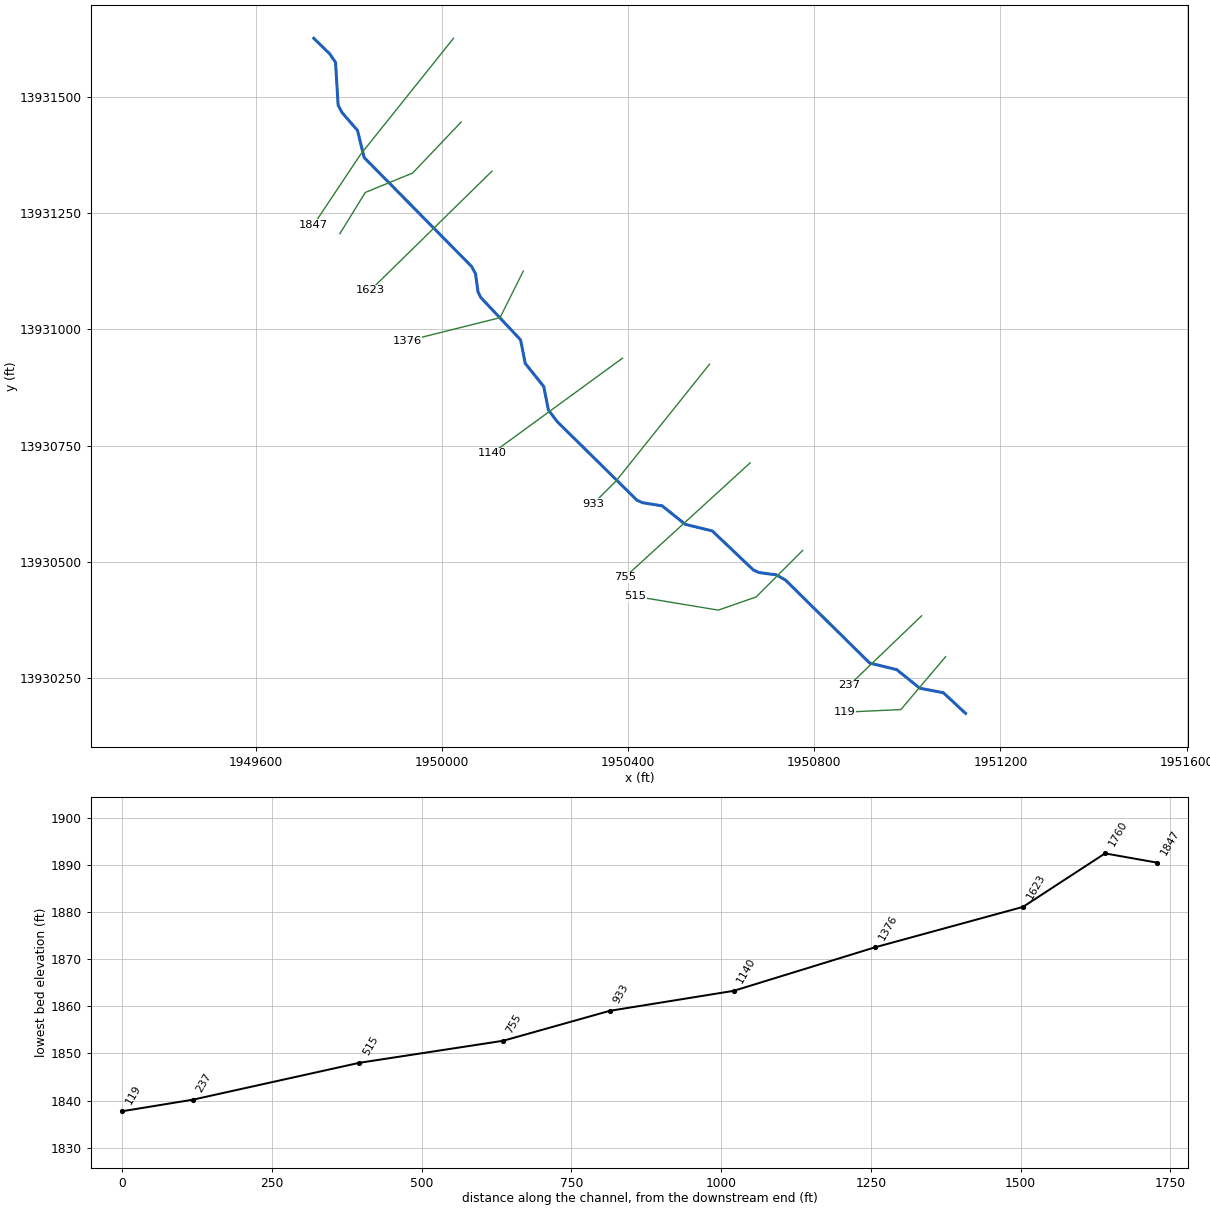
--- Stream0015.prj (project) ---

Proj Title=Stream0015 Base Level Engineering
Current Plan=p01
Default Exp/Contr=0.3,0.1
English Units
Geom File=g01
Flow File=f01
Plan File=p01
Y Axis Title=Elevation
X Axis Title(PF)=Main Channel Distance
X Axis Title(XS)=Station
BEGIN DESCRIPTION:
Stream0015
END DESCRIPTION:
DSS Export Rating Curves= 0
DSS Export Rating Curve Sorted= 0
DSS Export Volume Flow Curves= 0
DXF OffsetX= 0
DXF OffsetY= 0
DXF ScaleX= 1
DXF ScaleY= 10

--- Stream0015.p01 (plan) ---

Plan Title=Multiple Run
Short Identifier=Multiple
Geom File=g01
Flow File=f01
Subcritical Flow
K Sum by GR= 0
Std Step Tol= 0.01
Critical Tol= 0.01
Num of Std Step Trials= 20
Max Error Tol= 0.3
Flow Tol Ratio= 0.001
Split Flow NTrial= 30
Split Flow Tol= 0.02
Split Flow Ratio= 0.02
Log Output Level= 0
Friction Slope Method= 1
Unsteady Friction Slope Method= 2
Unsteady Bridges Friction Slope Method= 1
Parabolic Critical Depth
Global Vel Dist=  1 , 1 , 1
Global Log Level= 0
CheckData=True
Encroach Param= -1, 0, 0, 0
BEGIN DESCRIPTION:
Multiple Run
END DESCRIPTION:

--- Stream0015.f01 (steady flow) ---

Flow Title=Multiple
Number of Profiles=7
Profile Names=10-year,25-year,50-year,1pct_min,100-year,1pct_plu,500-year
River Rch & RM= Stream0015,Reach-1,1847
     489     788    1058     690    1377    2747    2293
Boundary for River Rch & Prof#=Stream0015,Reach-1,1
Up Type=0
Dn Type=3
Dn Slope=0.005
Boundary for River Rch & Prof#=Stream0015,Reach-1,2
Up Type=0
Dn Type=3
Dn Slope=0.005
Boundary for River Rch & Prof#=Stream0015,Reach-1,3
Up Type=0
Dn Type=3
Dn Slope=0.005
Boundary for River Rch & Prof#=Stream0015,Reach-1,4
Up Type=0
Dn Type=3
Dn Slope=0.005
Boundary for River Rch & Prof#=Stream0015,Reach-1,5
Up Type=0
Dn Type=3
Dn Slope=0.005
Boundary for River Rch & Prof#=Stream0015,Reach-1,6
Up Type=0
Dn Type=3
Dn Slope=0.005
Boundary for River Rch & Prof#=Stream0015,Reach-1,7
Up Type=0
Dn Type=3
Dn Slope=0.005

--- Stream0015.g01 (geometry) ---

Geom Title=Existing Conditions
Program Version=4.10

River Reach=Stream0015      ,Reach-1
Reach XY= 30
        1949725.       13931625.      1949758.88     13931592.05
      1949771.61      13931573.6       1949777.3     13931480.95
      1949785.83     13931465.34      1949818.86     13931427.17
      1949833.14     13931368.94      1950064.22     13931134.68
      1950072.47     13931118.95      1950077.54     13931081.05
      1950083.18     13931068.96      1950169.15     13930977.29
      1950179.19     13930926.73       1950218.9     13930877.19
      1950228.95     13930826.63      1950248.01     13930801.53
      1950418.94     13930633.14      1950431.04      13930627.5
      1950473.26     13930620.81      1950522.81      13930581.1
      1950581.05     13930566.84      1950668.96     13930483.18
      1950681.05     13930477.54      1950718.95     13930472.47
      1950738.21     13930461.37      1950918.94     13930283.14
      1950977.19      13930268.9      1951026.67     13930229.04
      1951077.36     13930219.33        1951125.       13930175.

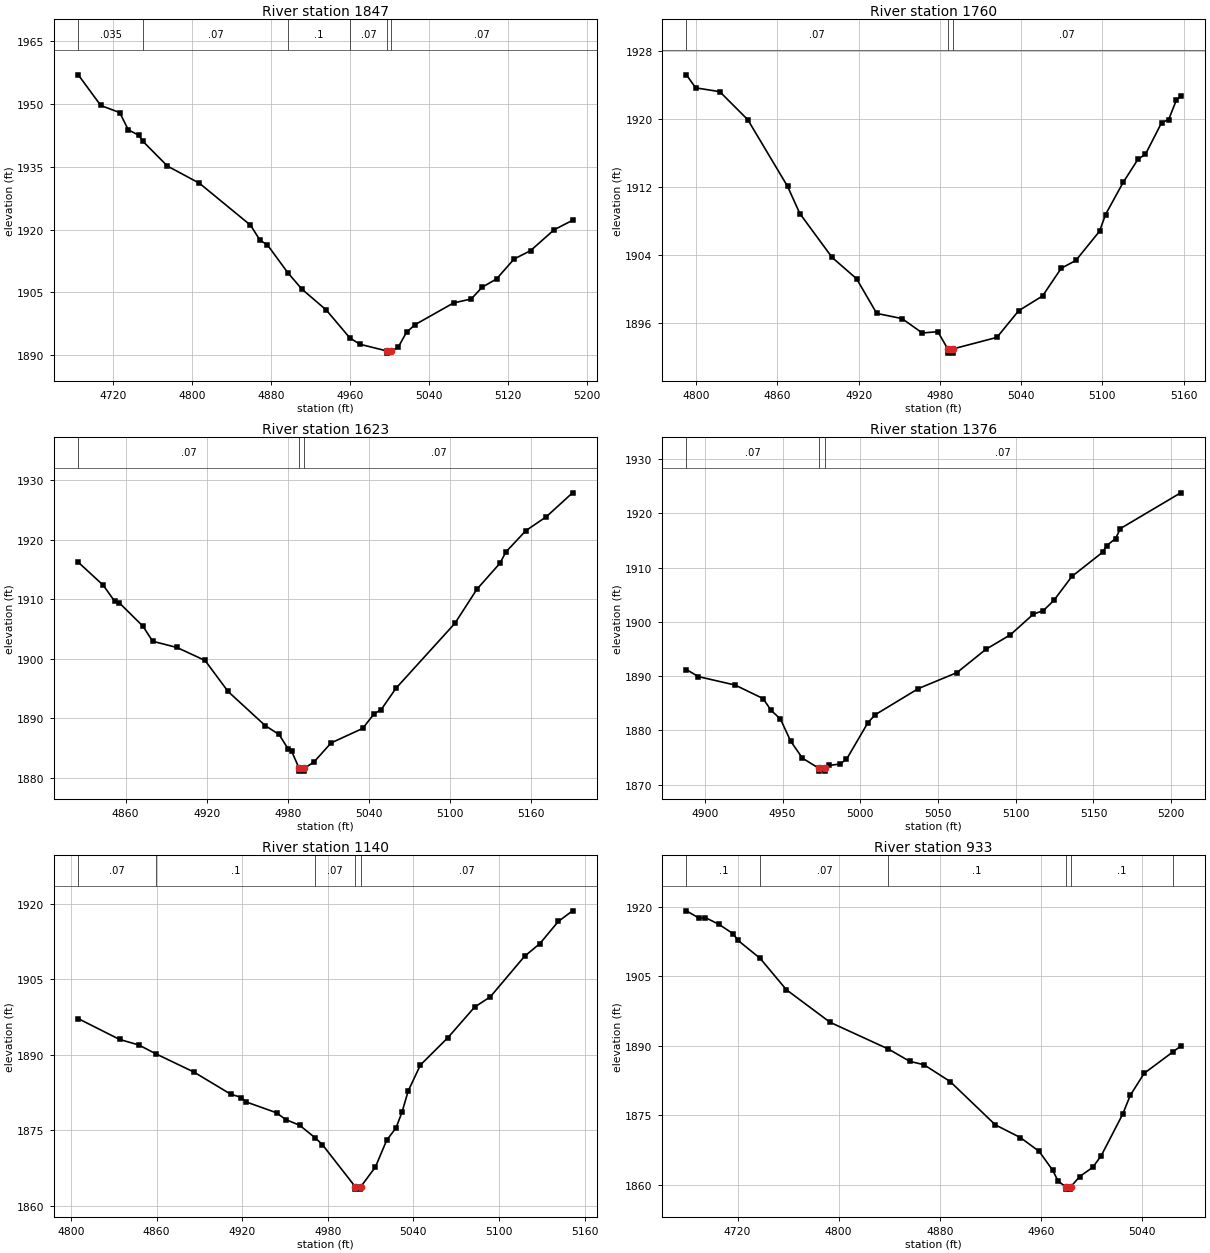
Type RM Length L Ch R = 1 ,1847    ,87,87,87
BEGIN DESCRIPTION:
Stream0015 4.0
END DESCRIPTION:
XS GIS Cut Line= 3
      1950025.02     13931625.02        1949825.       13931375.
      1949724.98     13931224.97
#Sta/Elev= 30
  4684.9 1956.97  4707.7 1949.64  4726.9 1947.95  4735.5 1943.84  4746.1 1942.54
  4750.5 1941.05  4775.1 1935.18  4807.6 1931.06  4859.3 1921.04    4869 1917.43
  4876.4 1916.34  4897.1 1909.68  4911.3 1905.77  4936.1 1900.75    4960 1894.06
  4970.3 1892.57  4997.7 1890.96  4997.9 1890.46  5001.7 1890.96  5008.8 1891.85
  5017.4 1895.48  5026.1 1897.28  5064.9 1902.45  5082.9 1903.41  5093.7 1906.18
  5108.5  1908.2  5126.2 1912.95  5142.9 1914.95  5166.7 1919.93  5185.4  1922.2
#Mann= 6 ,-1 , 0
  4684.9    .035       0  4750.5     .07       0  4897.1      .1       0
    4960     .07       0  4997.7     .05       0  5001.7     .07       0
Bank Sta=4997.7,5001.7
XS Rating Curve= 0 ,0
Exp/Cntr=0.3,0.1

Type RM Length L Ch R = 1 ,1760    ,137,137,137
BEGIN DESCRIPTION:
Stream0015 10.0
END DESCRIPTION:
XS GIS Cut Line= 4
      1950041.41     13931445.06      1949937.23     13931335.67
      1949835.67     13931294.01      1949780.98     13931205.47
#Sta/Elev= 30
  4792.9 1925.15  4799.7 1923.62  4817.5 1923.17  4838.2 1919.87  4867.6 1912.02
  4876.6 1908.84  4900.4 1903.68  4918.5 1901.17  4933.4 1897.09  4952.1 1896.48
    4967 1894.79  4978.5 1894.94  4985.8 1892.92  4986.1 1892.42  4989.6 1892.42
  4989.8 1892.92  5022.1 1894.27  5038.2 1897.41  5055.8 1899.14  5069.6  1902.4
  5080.4 1903.32  5097.9 1906.76  5102.3 1908.72  5115.3 1912.49  5126.3 1915.23
  5131.8 1915.81  5143.7 1919.52  5148.9 1919.89  5154.6 1922.17  5157.8 1922.61
#Mann= 3 ,-1 , 0
  4792.9     .07       0  4985.8     .05       0  4989.8     .07       0
Bank Sta=4985.8,4989.8
XS Rating Curve= 0 ,0
Exp/Cntr=0.3,0.1

Type RM Length L Ch R = 1 ,1623    ,247,247,247
BEGIN DESCRIPTION:
Mapping XS 966517f9
END DESCRIPTION:
XS GIS Cut Line= 2
      1950107.86     13931339.81      1949846.42     13931083.68
#Sta/Elev= 30
  4824.9 1916.21  4843.4 1912.34  4851.8 1909.66  4855.2  1909.4  4872.8 1905.45
    4880 1902.92    4898 1901.87  4918.8 1899.69  4935.8 1894.48  4963.3 1888.74
  4973.6 1887.24  4980.3 1884.82  4982.9 1884.43  4988.4 1881.58  4988.6 1881.08
  4992.1 1881.08  4992.4 1881.58  4999.4  1882.6  5012.1 1885.82  5035.5 1888.26
    5044 1890.72  5049.2 1891.42  5060.1    1895  5103.8 1905.93  5120.1 1911.67
  5137.2 1916.05  5141.5 1917.92  5156.4 1921.53  5171.5 1923.86  5190.9 1927.88
#Mann= 3 ,-1 , 0
  4824.9     .07       0  4988.4     .05       0  4992.4     .07       0
Bank Sta=4988.4,4992.4
XS Rating Curve= 0 ,0
Exp/Cntr=0.3,0.1

Type RM Length L Ch R = 1 ,1376    ,236,236,236
BEGIN DESCRIPTION:
Stream0015 3.0
END DESCRIPTION:
XS GIS Cut Line= 3
      1950174.99     13931124.98        1950125.       13931025.
      1949925.04     13930975.01
#Sta/Elev= 30
  4888.2 1891.22  4895.8 1889.92  4919.6 1888.35  4937.5 1885.87  4942.7 1883.68
  4948.6 1882.13  4955.3 1878.01  4962.8  1874.9  4973.5 1873.01  4973.7 1872.51
  4977.2 1872.51  4977.5 1873.01  4979.9 1873.55  4986.7 1873.81  4991.1 1874.66
    5005 1881.46  5009.6 1882.89  5037.4 1887.71  5062.2 1890.65  5080.7 1894.92
  5096.6 1897.62  5111.4 1901.43  5117.8 1902.07  5124.5 1903.94  5136.1 1908.35
  5155.9 1912.82  5158.4    1914  5164.2 1915.33  5167.3 1917.17  5206.1 1923.75
#Mann= 3 ,-1 , 0
  4888.2     .07       0  4973.5     .05       0  4977.5     .07       0
Bank Sta=4973.5,4977.5
XS Rating Curve= 0 ,0
Exp/Cntr=0.3,0.1

Type RM Length L Ch R = 1 ,1140    ,207,207,207
BEGIN DESCRIPTION:
Mapping XS 5c92ba97
END DESCRIPTION:
XS GIS Cut Line= 2
      1950388.07     13930938.01      1950108.15     13930733.79
#Sta/Elev= 30
  4805.1 1897.18  4834.1 1893.04  4847.5 1891.95  4859.7 1890.16  4886.1 1886.57
  4911.9 1882.17  4919.5  1881.5  4922.6 1880.64  4944.1 1878.46  4950.5 1877.12
  4960.3 1875.98  4971.3 1873.45  4976.3 1872.11  4999.2 1863.78  4999.4 1863.28
  5002.9 1863.28  5003.2 1863.78  5013.4 1867.67  5021.4 1873.05  5027.8 1875.42
  5032.1 1878.61  5036.4 1882.81    5045 1887.98  5064.3 1893.42  5082.9 1899.46
    5094 1901.53    5118 1909.59  5128.7  1912.1  5141.6  1916.5  5151.6 1918.62
#Mann= 5 ,-1 , 0
  4805.1     .07       0  4859.7      .1       0  4971.3     .07       0
  4999.2     .05       0  5003.2     .07       0
Bank Sta=4999.2,5003.2
XS Rating Curve= 0 ,0
Exp/Cntr=0.3,0.1

Type RM Length L Ch R = 1 ,933     ,178,178,178
BEGIN DESCRIPTION:
Stream0015 2.0
END DESCRIPTION:
XS GIS Cut Line= 3
      1950575.02     13930925.03        1950375.       13930675.
        1950325.       13930625.
#Sta/Elev= 30
  4679.6  1919.1  4689.6 1917.52  4694.6 1917.63    4705 1916.23  4716.5 1914.17
  4720.3 1912.74  4737.9 1908.84  4758.7 1902.06  4793.3 1895.03  4839.4 1889.26
  4856.2 1886.62  4867.5 1885.88  4888.2 1882.25  4923.9 1872.91  4943.7 1870.17
  4958.5  1867.2  4969.3 1863.11  4973.5 1860.78  4979.6 1859.54  4979.8 1859.04
  4983.3 1859.04  4983.6 1859.54  4990.6 1861.76  5000.9 1863.73  5007.6 1866.23
  5024.6  1875.2  5030.6 1879.27  5041.6 1884.03  5064.7 1888.73  5070.5 1889.89
#Mann= 6 ,-1 , 0
  4679.6      .1       0  4737.9     .07       0  4839.4      .1       0
  4979.6     .05       0  4983.6      .1       0  5064.7     .07       0
Bank Sta=4979.6,4983.6
XS Rating Curve= 0 ,0
Exp/Cntr=0.3,0.1

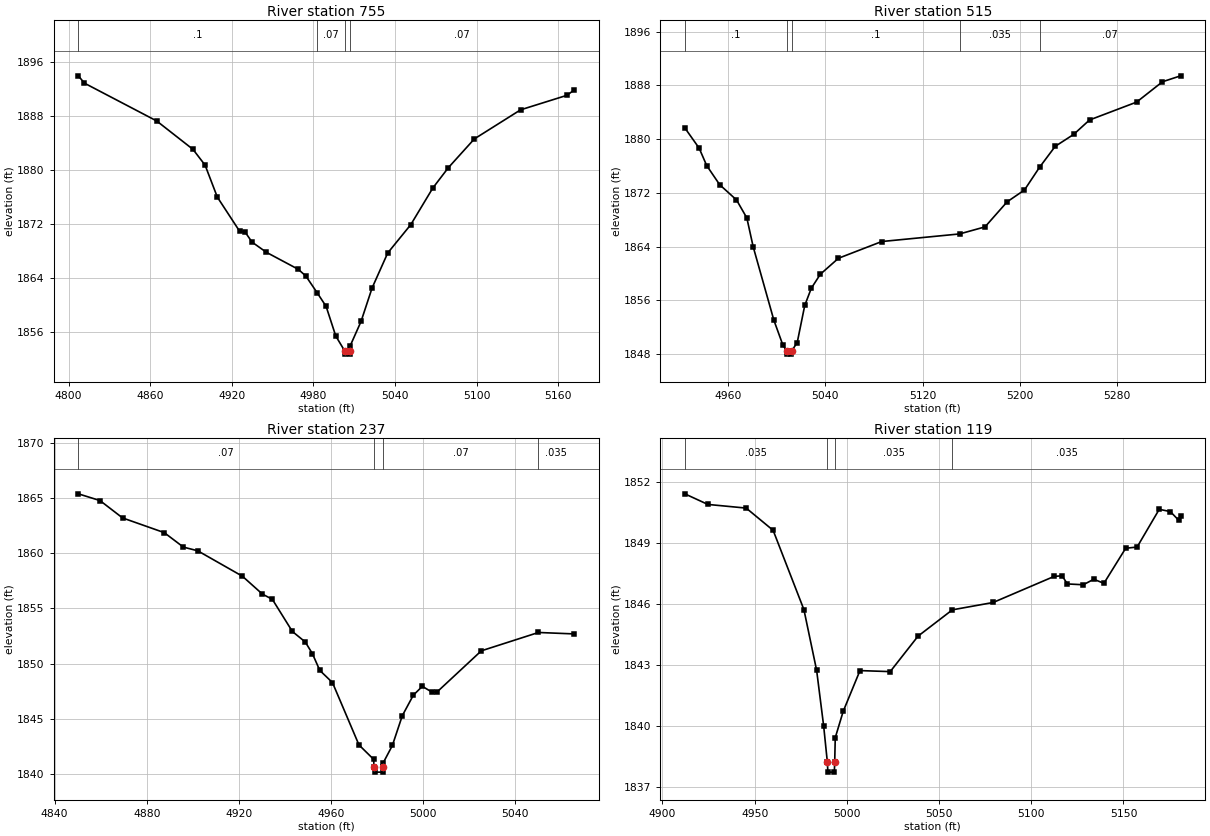
Type RM Length L Ch R = 1 ,755     ,240,240,240
BEGIN DESCRIPTION:
Mapping XS adf9ea7c
END DESCRIPTION:
XS GIS Cut Line= 2
      1950662.24     13930713.05      1950392.93     13930467.27
#Sta/Elev= 30
  4807.1 1894.02  4811.6 1892.93  4864.7 1887.32  4891.4  1883.1  4900.3 1880.76
  4909.3 1876.01  4925.7 1870.94  4929.7 1870.83  4934.8 1869.33  4945.4 1867.81
  4968.8 1865.29  4974.4 1864.29  4982.6 1861.84  4989.3 1859.78  4996.4 1855.38
  5002.9 1853.19  5003.1 1852.69  5006.6 1852.69  5006.9 1853.19  5007.1 1853.96
    5015 1857.55  5023.1 1862.51  5034.6 1867.71  5051.6 1871.93  5067.8 1877.37
  5079.2 1880.38  5098.3 1884.65  5132.3 1888.97  5166.3 1891.12  5171.7 1891.91
#Mann= 4 ,-1 , 0
  4807.1      .1       0  4982.6     .07       0  5002.9     .05       0
  5006.9     .07       0
Bank Sta=5002.9,5006.9
XS Rating Curve= 0 ,0
Exp/Cntr=0.3,0.1

Type RM Length L Ch R = 1 ,515     ,278,278,278
BEGIN DESCRIPTION:
Stream0015 1.0
END DESCRIPTION:
XS GIS Cut Line= 5
      1950774.99     13930524.99        1950725.       13930475.
        1950675.       13930425.      1950593.86      13930396.8
      1950415.99     13930426.28
#Sta/Elev= 30
  4924.5 1881.68  4936.3 1878.66  4942.5 1876.07  4953.2 1873.22    4967 1870.96
  4975.5 1868.28  4980.7    1864  4997.7 1853.08  5005.2 1849.33  5008.4 1848.52
  5008.7 1848.02  5012.2 1848.02  5012.4 1848.52  5016.9 1849.73  5023.1 1855.26
  5028.5 1857.82  5035.9  1859.9  5050.8 1862.28  5086.4 1864.77  5150.4  1865.9
  5171.3 1866.95  5189.5 1870.68  5203.7 1872.43  5216.1 1875.81    5229 1878.93
  5244.2 1880.71  5257.2 1882.85  5295.9 1885.51  5317.2 1888.54  5332.1 1889.42
#Mann= 5 ,-1 , 0
  4924.5      .1       0  5008.4     .05       0  5012.4      .1       0
  5150.4    .035       0  5216.1     .07       0
Bank Sta=5008.4,5012.4
XS Rating Curve= 0 ,0
Exp/Cntr=0.3,0.1

Type RM Length L Ch R = 1 ,237     ,118,118,118
BEGIN DESCRIPTION:
Stream0015 0.0
END DESCRIPTION:
XS GIS Cut Line= 2
      1951030.59     13930384.55      1950875.28     13930235.58
#Sta/Elev= 30
  4850.3 1865.37  4859.7 1864.76  4869.5 1863.19  4887.6 1861.86  4895.9 1860.55
  4902.1 1860.22  4921.5 1857.92  4930.2  1856.3  4934.5 1855.83  4943.2 1852.92
  4948.8 1851.97  4951.9 1850.91  4955.1  1849.4  4960.6  1848.3  4972.1 1842.66
  4978.5 1841.35  4978.6  1840.7  4978.9  1840.2  4982.4  1840.2  4982.6  1840.7
  4982.7 1841.07  4986.6 1842.61  4990.9  1845.3  4995.7 1847.16  4999.6 1847.96
  5003.9 1847.42  5006.1 1847.47  5025.2 1851.17    5050 1852.83  5065.5  1852.7
#Mann= 4 ,-1 , 0
  4850.3     .07       0  4978.6     .05       0  4982.6     .07       0
    5050    .035       0
Bank Sta=4978.6,4982.6
XS Rating Curve= 0 ,0
Exp/Cntr=0.3,0.1

Type RM Length L Ch R = 1 ,119     ,0,0,0
BEGIN DESCRIPTION:
Stream0015 0.1
END DESCRIPTION:
XS GIS Cut Line= 3
      1951082.17     13930296.79      1950986.04     13930183.17
      1950866.09     13930177.62
#Sta/Elev= 30
  4912.1  1851.4  4924.6 1850.88  4945.4  1850.7    4960 1849.61  4976.7 1845.72
  4983.6 1842.74  4987.4 1840.02  4989.4 1838.25  4989.7 1837.75  4993.2 1837.75
  4993.4 1838.25  4993.7 1839.44    4998 1840.73  5007.1 1842.73  5023.5 1842.68
  5038.6 1844.42  5057.2 1845.71  5079.3 1846.07  5112.4 1847.35  5116.7 1847.38
  5119.6 1846.98  5128.2 1846.94  5133.9 1847.21  5139.4 1847.01  5151.2 1848.73
  5157.4 1848.79  5169.4 1850.64  5175.4 1850.53  5179.9 1850.11    5181 1850.31
#Mann= 4 ,-1 , 0
  4912.1    .035       0  4989.4    .035       0  4993.4    .035       0
  5057.2    .035       0
Bank Sta=4989.4,4993.4
XS Rating Curve= 0 ,0
Exp/Cntr=0.3,0.1

Chan Stop Cuts=-1
Use User Specified Reach Order=0
Composite Channel Slope=5