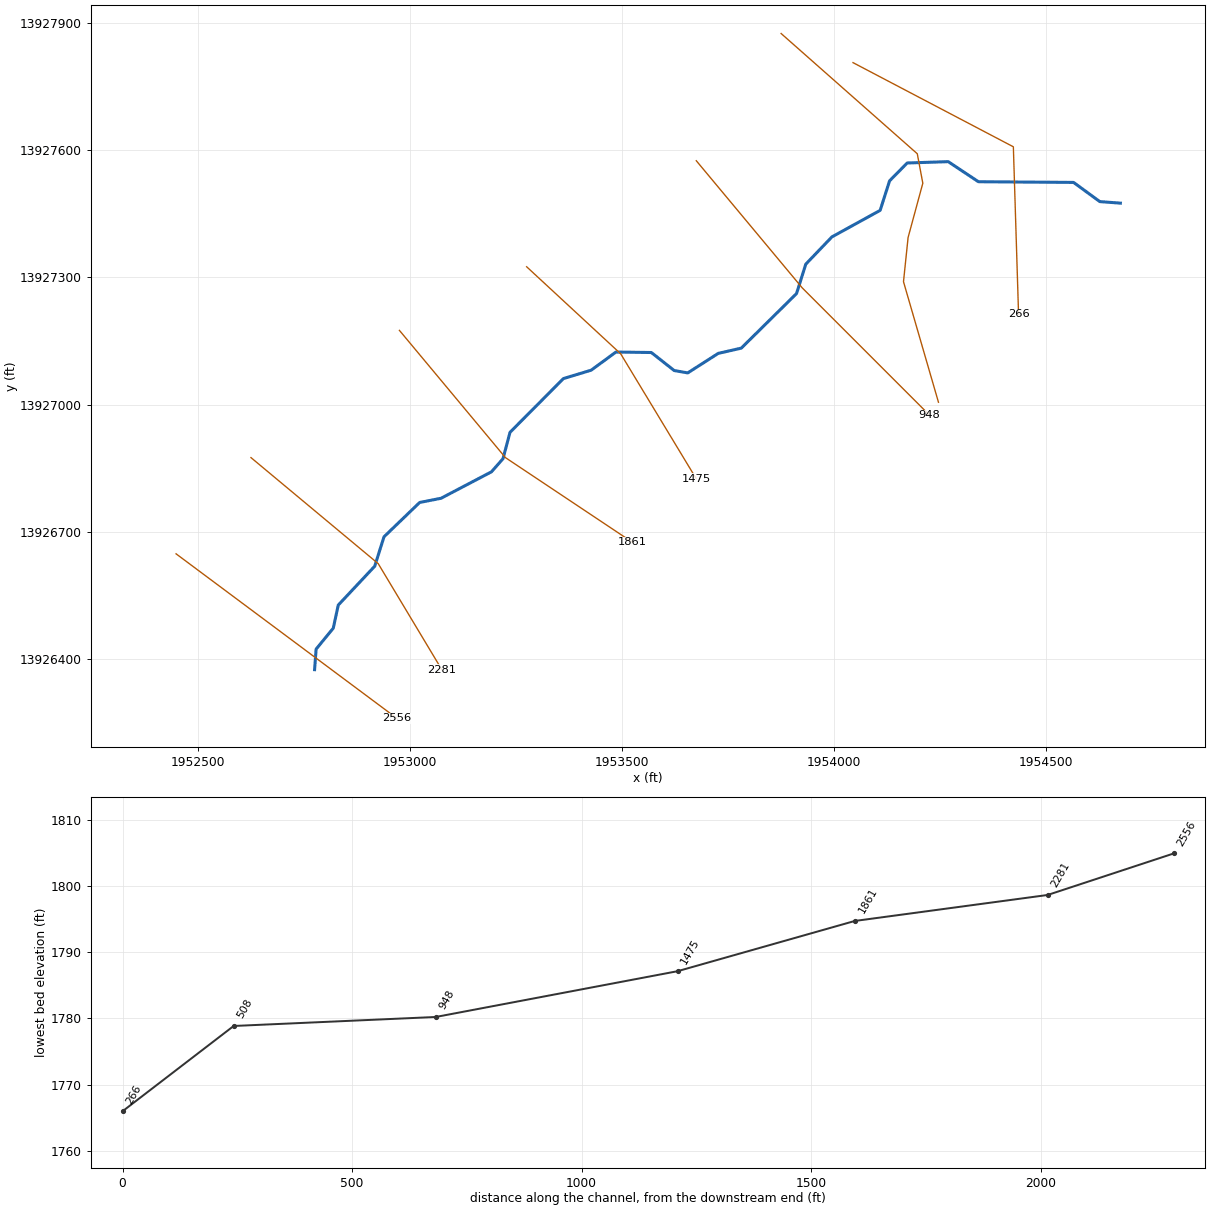
--- Stream0016.prj (project) ---

Proj Title=Stream0016 Base Level Engineering
Current Plan=p01
Default Exp/Contr=0.3,0.1
English Units
Geom File=g01
Flow File=f01
Plan File=p01
BEGIN DESCRIPTION:
Stream0016
END DESCRIPTION:

--- Stream0016.p01 (plan) ---

Plan Title=Multiple Run
Short Identifier=Multiple
Geom File=g01
Flow File=f01
Subcritical Flow
K Sum by GR= 0
Std Step Tol= 0.01
Critical Tol= 0.01
Num of Std Step Trials= 20
Max Error Tol= 0.3
Flow Tol Ratio= 0.001
Split Flow NTrial= 30
Split Flow Tol= 0.02
Split Flow Ratio= 0.02
Log Output Level= 0
Friction Slope Method= 1
Unsteady Friction Slope Method= 2
Unsteady Bridges Friction Slope Method= 1
Parabolic Critical Depth
Global Vel Dist=  1 , 1 , 1
Global Log Level= 0
CheckData=True
Encroach Param= -1, 0, 0, 0
BEGIN DESCRIPTION:
Multiple Run
END DESCRIPTION:

--- Stream0016.f01 (steady flow) ---

Flow Title=Multiple
Number of Profiles=7
Profile Names=10-year,25-year,50-year,1pct_min,100-year,1pct_plu,500-year
River Rch & RM= Stream0016,Reach-1,2556
    1066    1810    2518    1696    3383    6750    6022
Boundary for River Rch & Prof#=Stream0016,Reach-1,1
Up Type=0
Dn Type=3
Dn Slope=0.005
Boundary for River Rch & Prof#=Stream0016,Reach-1,2
Up Type=0
Dn Type=3
Dn Slope=0.005
Boundary for River Rch & Prof#=Stream0016,Reach-1,3
Up Type=0
Dn Type=3
Dn Slope=0.005
Boundary for River Rch & Prof#=Stream0016,Reach-1,4
Up Type=0
Dn Type=3
Dn Slope=0.005
Boundary for River Rch & Prof#=Stream0016,Reach-1,5
Up Type=0
Dn Type=3
Dn Slope=0.005
Boundary for River Rch & Prof#=Stream0016,Reach-1,6
Up Type=0
Dn Type=3
Dn Slope=0.005
Boundary for River Rch & Prof#=Stream0016,Reach-1,7
Up Type=0
Dn Type=3
Dn Slope=0.005

--- Stream0016.g01 (geometry) ---

Geom Title=Existing Conditions

River Reach=Stream0016,Reach-1
Reach XY= 30
      1952775.00     13926375.00      1952778.60     13926423.51
      1952819.03     13926472.76      1952830.83     13926527.30
      1952916.82     13926618.96      1952938.62     13926688.24
      1953022.69     13926769.17      1953073.26     13926779.19
      1953192.05     13926841.49      1953219.25     13926872.46
      1953235.79     13926934.66      1953361.78     13927061.38
      1953427.17     13927081.15      1953485.54     13927123.92
      1953569.03     13927122.81      1953622.82     13927080.38
      1953654.83     13927074.71      1953726.74     13927120.75
      1953781.06     13927133.14      1953911.37     13927261.79
      1953933.15     13927331.07      1953994.77     13927395.41
      1954108.50     13927457.96      1954130.75     13927527.56
      1954172.33     13927569.70      1954269.02     13927572.84
      1954340.22     13927525.52      1954564.54     13927523.88
      1954626.51     13927478.65      1954675.00     13927475.00

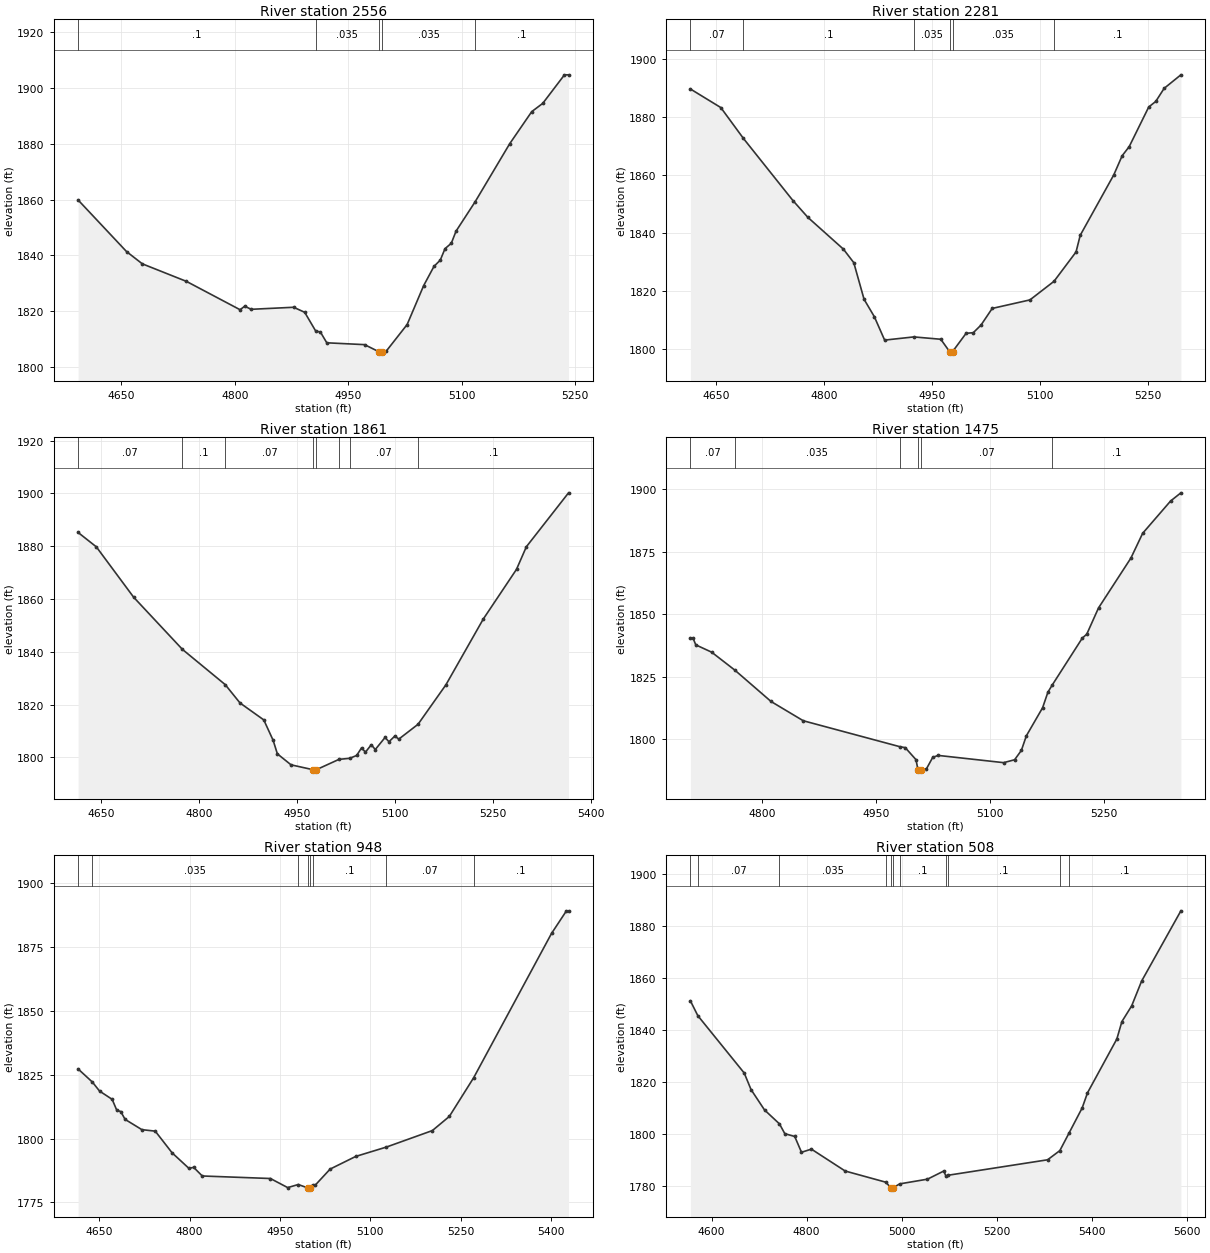
Type RM Length L Ch R = 1,2556,275,275,275
BEGIN DESCRIPTION:
Stream0016 6.0
END DESCRIPTION:
XS GIS Cut Line= 2
      1952448.36     13926648.18      1952968.65     13926260.56
#Sta/Elev= 30
  4592.7 1859.85  4656.8 1841.36  4677.7 1836.96  4736.1 1830.67  4807.0 1820.52
  4813.2 1821.79  4821.6 1820.67  4877.9 1821.40  4892.5 1819.59  4906.9 1812.95
  4913.3 1812.51  4921.7 1808.67  4971.7 1808.01  4990.6 1805.47  4990.8 1804.97
  4994.6 1805.47  5000.0 1805.56  5028.0 1815.22  5049.9 1829.19  5063.5 1836.05
  5071.8 1838.28  5078.1 1842.40  5086.4 1844.33  5092.7 1848.68  5118.0 1859.22
  5163.6 1879.97  5192.8 1891.49  5207.4 1894.46  5236.1 1904.68  5241.5 1904.68
#Mann=5,-1,0
  4592.7     0.1       0  4906.9   0.035       0  4990.6   0.035       0
  4994.6   0.035       0  5118.0     0.1       0
Bank Sta=4990.6,4994.6
Exp/Cntr=0.3,0.1

Type RM Length L Ch R = 1,2281,420,420,420
BEGIN DESCRIPTION:
Stream0016 5.0
END DESCRIPTION:
XS GIS Cut Line= 3
      1952624.99     13926875.01      1952925.00     13926625.00
      1953075.01     13926374.98
#Sta/Elev= 30
  4614.1 1889.74  4656.4 1883.33  4687.8 1872.70  4756.7 1851.27  4777.5 1845.47
  4826.9 1834.52  4841.3 1829.86  4855.6 1817.24  4869.9 1811.23  4884.2 1803.17
  4924.8 1804.27  4962.3 1803.46  4974.6 1799.18  4974.9 1798.68  4978.6 1799.18
  4997.5 1805.51  5007.5 1805.73  5018.2 1808.34  5033.8 1814.09  5086.3 1817.03
  5119.8 1823.45  5150.4 1833.56  5156.2 1839.30  5202.9 1860.14  5214.5 1866.72
  5224.3 1869.86  5251.5 1883.54  5261.2 1885.43  5272.9 1889.95  5296.2 1894.62
#Mann=6,-1,0
  4614.1    0.07       0  4687.8     0.1       0  4924.8   0.035       0
  4974.6   0.035       0  4978.6   0.035       0  5119.8     0.1       0
Bank Sta=4974.6,4978.6
Exp/Cntr=0.3,0.1

Type RM Length L Ch R = 1,1861,386,386,386
BEGIN DESCRIPTION:
Stream0016 4.0
END DESCRIPTION:
XS GIS Cut Line= 3
      1952975.01     13927174.99      1953225.00     13926875.00
      1953525.04     13926674.97
#Sta/Elev= 30
  4614.4 1885.21  4642.4 1879.74  4699.6 1860.63  4774.2 1840.89  4839.8 1827.52
  4862.4 1820.58  4898.8 1814.16  4913.1 1806.44  4919.6 1801.30  4940.5 1797.14
  4974.9 1795.25  4975.2 1794.75  4978.9 1795.25  5013.9 1799.20  5030.3 1799.61
  5041.0 1800.68  5048.5 1803.56  5054.5 1801.95  5063.5 1804.76  5069.5 1802.92
  5084.5 1807.50  5090.5 1805.89  5099.5 1808.04  5105.6 1806.89  5135.0 1812.50
  5177.7 1827.46  5234.8 1852.34  5285.8 1871.22  5300.9 1879.78  5365.5 1900.22
#Mann=8,-1,0
  4614.4    0.07       0  4774.2     0.1       0  4839.8    0.07       0
  4974.9    0.05       0  4978.9    0.07       0  5013.9   0.035       0
  5030.3    0.07       0  5135.0     0.1       0
Bank Sta=4974.9,4978.9
Exp/Cntr=0.3,0.1

Type RM Length L Ch R = 1,1475,527,527,527
BEGIN DESCRIPTION:
Stream0016 3.0
END DESCRIPTION:
XS GIS Cut Line= 3
      1953274.99     13927325.01      1953496.84     13927119.63
      1953674.99     13926825.02
#Sta/Elev= 30
  4705.2 1840.38  4708.6 1840.38  4712.3 1837.66  4733.3 1834.72  4763.7 1827.57
  4811.5 1815.01  4854.0 1807.30  4981.5 1796.91  4988.4 1796.55  5002.6 1791.73
  5005.2 1787.65  5005.5 1787.15  5009.2 1787.65  5016.2 1787.98  5024.6 1792.63
  5031.7 1793.44  5118.1 1790.54  5132.6 1791.70  5141.5 1795.44  5148.1 1801.29
  5169.5 1812.51  5176.5 1818.74  5182.4 1821.69  5221.8 1840.36  5227.7 1841.93
  5243.2 1852.43  5285.9 1872.38  5301.4 1882.29  5338.2 1895.20  5351.8 1898.48
#Mann=6,-1,0
  4705.2    0.07       0  4763.7   0.035       0  4981.5    0.07       0
  5005.2    0.05       0  5009.2    0.07       0  5182.4     0.1       0
Bank Sta=5005.2,5009.2
Exp/Cntr=0.3,0.1

Type RM Length L Ch R = 1,948,440,440,440
BEGIN DESCRIPTION:
Stream0016 2.0
END DESCRIPTION:
XS GIS Cut Line= 3
      1953675.03     13927574.96      1953925.00     13927275.00
      1954224.98     13926975.02
#Sta/Elev= 30
  4614.6 1827.22  4638.4 1822.07  4650.3 1818.55  4671.2 1815.33  4679.0 1811.01
  4685.5 1810.56  4692.7 1807.49  4720.6 1803.47  4742.8 1802.89  4770.8 1794.41
  4798.7 1788.35  4806.6 1788.73  4820.9 1785.36  4934.1 1784.37  4962.8 1780.82
  4980.3 1782.02  4995.9 1780.72  4996.2 1780.22  4999.9 1780.72  5004.1 1781.79
  5008.6 1781.79  5033.3 1788.06  5075.8 1793.00  5126.8 1796.67  5203.1 1803.11
  5231.3 1808.64  5271.8 1823.81  5401.0 1880.17  5425.8 1889.02  5429.3 1889.02
#Mann=8,-1,0
  4614.6     0.1       0  4638.4   0.035       0  4980.3    0.07       0
  4995.9    0.05       0  4999.9    0.07       0  5004.1     0.1       0
  5126.8    0.07       0  5271.8     0.1       0
Bank Sta=4995.9,4999.9
Exp/Cntr=0.3,0.1

Type RM Length L Ch R = 1,508,242,242,242
BEGIN DESCRIPTION:
Stream0016 1.0
END DESCRIPTION:
XS GIS Cut Line= 6
      1953875.01     13927874.99      1954196.11     13927591.43
      1954209.13     13927521.99      1954174.41     13927393.95
      1954163.56     13927289.78      1954246.02     13927005.53
#Sta/Elev= 30
  4555.4 1851.26  4571.0 1845.56  4668.7 1823.50  4683.0 1817.15  4711.4 1809.31
  4742.9 1803.94  4754.1 1800.19  4775.0 1799.10  4789.2 1793.03  4810.1 1794.24
  4881.2 1785.82  4966.4 1781.54  4977.7 1779.36  4978.0 1778.86  4981.7 1779.36
  4996.0 1780.88  5054.4 1782.69  5088.5 1785.80  5093.7 1783.75  5096.8 1784.17
  5307.2 1790.14  5333.0 1793.67  5352.2 1800.36  5380.1 1810.12  5391.2 1815.88
  5453.0 1836.60  5463.6 1843.28  5484.2 1849.33  5505.1 1858.85  5587.8 1885.88
#Mann=11,-1,0
  4555.4     0.1       0  4571.0    0.07       0  4742.9   0.035       0
  4966.4    0.07       0  4977.7    0.05       0  4981.7    0.07       0
  4996.0     0.1       0  5093.7    0.07       0  5096.8     0.1       0
  5333.0    0.07       0  5352.2     0.1       0
Bank Sta=4977.7,4981.7
Exp/Cntr=0.3,0.1

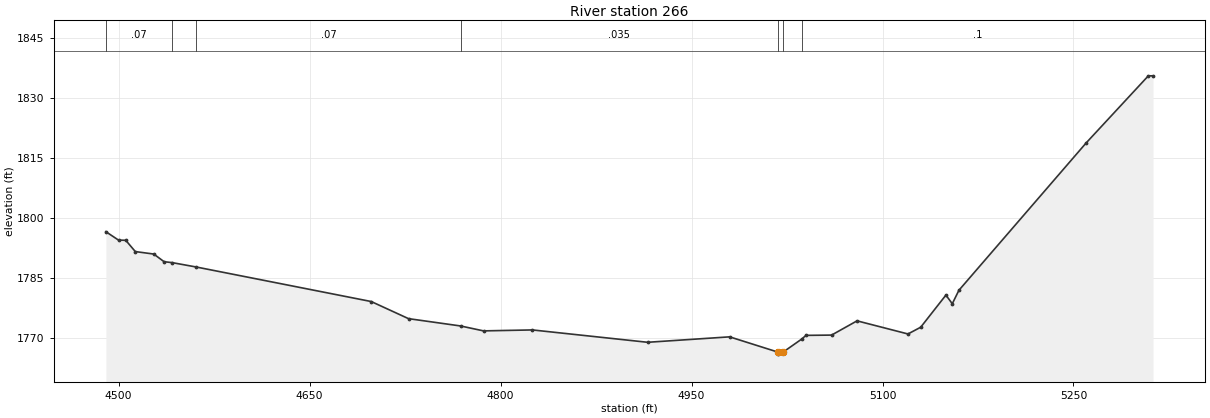
Type RM Length L Ch R = 1,266,0,0,0
BEGIN DESCRIPTION:
Stream0016 0.0
END DESCRIPTION:
XS GIS Cut Line= 3
      1954044.52     13927806.33      1954422.61     13927607.87
      1954434.91     13927212.57
#Sta/Elev= 30
  4490.0 1796.57  4499.9 1794.47  4505.6 1794.42  4513.1 1791.60  4527.6 1790.98
  4535.7 1789.07  4542.2 1788.83  4561.0 1787.74  4698.4 1779.11  4727.7 1774.83
  4768.6 1773.00  4786.6 1771.77  4825.0 1772.01  4915.5 1768.92  4979.9 1770.28
  5017.9 1766.46  5018.2 1765.96  5021.9 1766.46  5036.5 1769.72  5039.9 1770.65
  5060.0 1770.72  5080.0 1774.28  5120.0 1771.00  5130.0 1772.69  5149.8 1780.72
  5154.8 1778.56  5160.0 1781.92  5260.0 1818.78  5308.8 1835.54  5312.5 1835.54
#Mann=7,-1,0
  4490.0    0.07       0  4542.2   0.035       0  4561.0    0.07       0
  4768.6   0.035       0  5017.9   0.035       0  5021.9   0.035       0
  5036.5     0.1       0
Bank Sta=5017.9,5021.9
Exp/Cntr=0.3,0.1

Chan Stop Cuts=-1