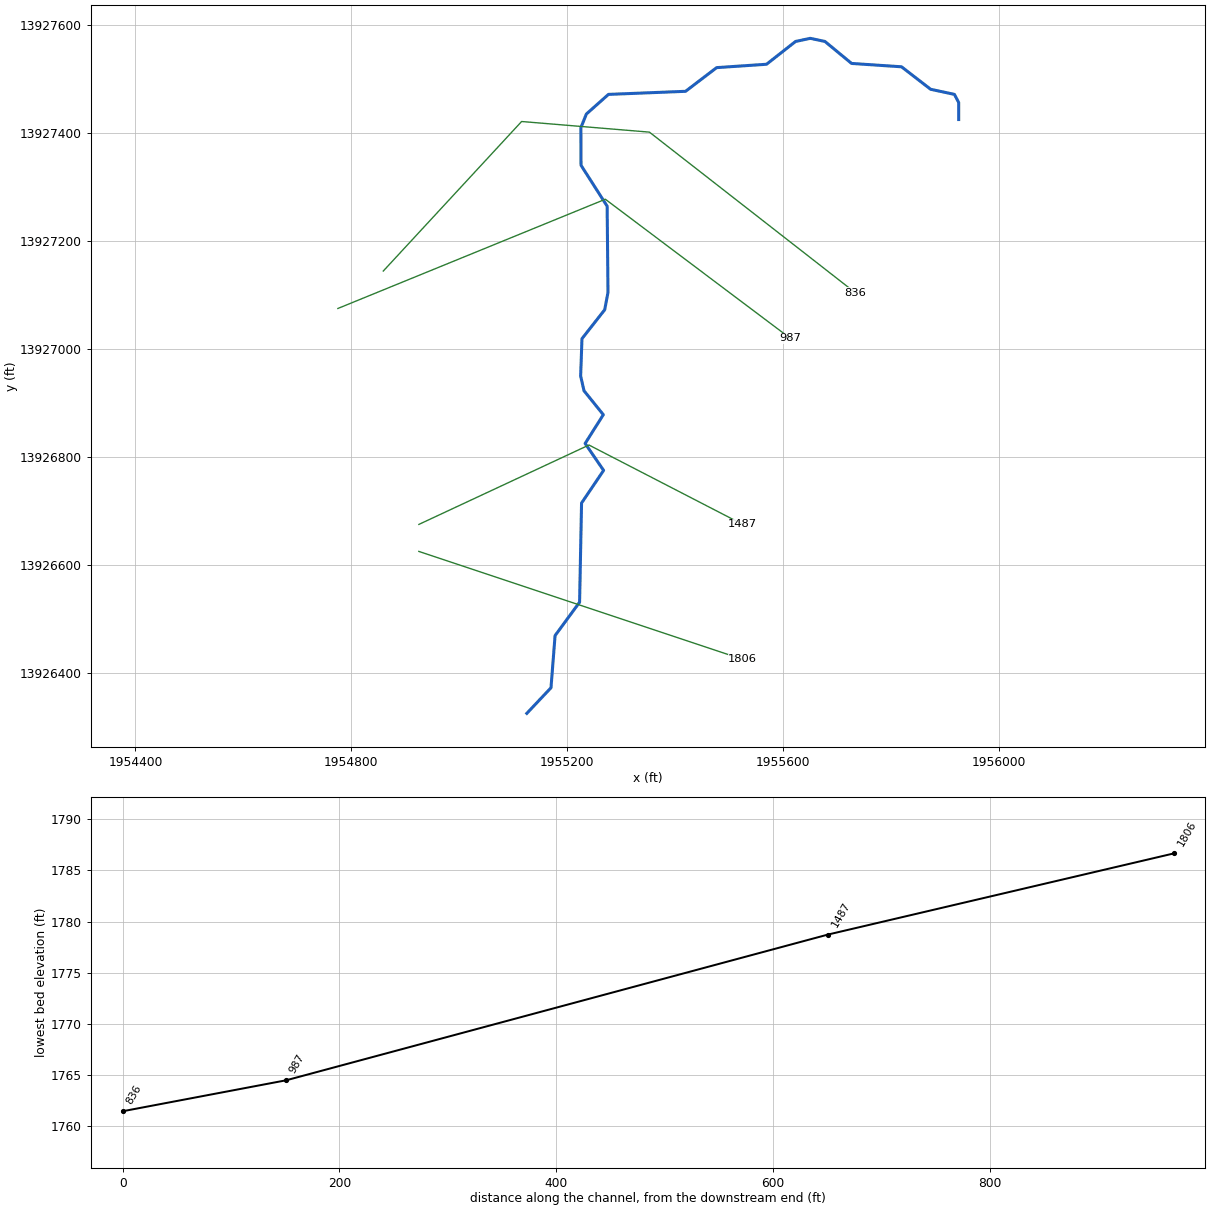
--- Stream0017.prj (project) ---

Proj Title=Stream0017 Base Level Engineering
Current Plan=p01
Default Exp/Contr=0.3,0.1
English Units
Geom File=g01
Flow File=f01
Plan File=p01
BEGIN DESCRIPTION:
Stream0017
END DESCRIPTION:

--- Stream0017.p01 (plan) ---

Plan Title=Multiple Run
Short Identifier=Multiple
Geom File=g01
Flow File=f01
Subcritical Flow
K Sum by GR= 0
Std Step Tol= 0.01
Critical Tol= 0.01
Num of Std Step Trials= 20
Max Error Tol= 0.3
Flow Tol Ratio= 0.001
Split Flow NTrial= 30
Split Flow Tol= 0.02
Split Flow Ratio= 0.02
Log Output Level= 0
Friction Slope Method= 1
Unsteady Friction Slope Method= 2
Unsteady Bridges Friction Slope Method= 1
Parabolic Critical Depth
Global Vel Dist=  1 , 1 , 1
Global Log Level= 0
CheckData=True
Encroach Param= -1, 0, 0, 0
BEGIN DESCRIPTION:
Multiple Run
END DESCRIPTION:

--- Stream0017.f01 (steady flow) ---

Flow Title=Multiple
Number of Profiles=7
Profile Names=10-year,25-year,50-year,1pct_min,100-year,1pct_plu,500-year
River Rch & RM= Stream0017,Reach-1,1806
     555     905    1226     807    1610    3213    2731
Boundary for River Rch & Prof#=Stream0017,Reach-1,1
Up Type=0
Dn Type=3
Dn Slope=0.005
Boundary for River Rch & Prof#=Stream0017,Reach-1,2
Up Type=0
Dn Type=3
Dn Slope=0.005
Boundary for River Rch & Prof#=Stream0017,Reach-1,3
Up Type=0
Dn Type=3
Dn Slope=0.005
Boundary for River Rch & Prof#=Stream0017,Reach-1,4
Up Type=0
Dn Type=3
Dn Slope=0.005
Boundary for River Rch & Prof#=Stream0017,Reach-1,5
Up Type=0
Dn Type=3
Dn Slope=0.005
Boundary for River Rch & Prof#=Stream0017,Reach-1,6
Up Type=0
Dn Type=3
Dn Slope=0.005
Boundary for River Rch & Prof#=Stream0017,Reach-1,7
Up Type=0
Dn Type=3
Dn Slope=0.005

--- Stream0017.g01 (geometry) ---

Geom Title=Existing Conditions

River Reach=Stream0017,Reach-1
Reach XY= 30
      1955125.00     13926325.00      1955169.78     13926372.45
      1955177.32     13926469.04      1955222.74     13926530.94
      1955226.38     13926714.57      1955267.22     13926775.10
      1955233.03     13926825.00      1955266.73     13926878.22
      1955230.94     13926922.57      1955224.68     13926949.96
      1955227.17     13927019.02      1955269.25     13927072.66
      1955275.36     13927104.85      1955273.78     13927264.50
      1955225.37     13927340.28      1955225.18     13927409.93
      1955235.28     13927435.16      1955276.22     13927471.56
      1955419.06     13927477.27      1955476.60     13927521.14
      1955569.03     13927527.38      1955622.82     13927569.63
      1955650.00     13927575.40      1955677.18     13927569.63
      1955726.58     13927528.89      1955819.06     13927522.69
      1955873.00     13927481.04      1955917.01     13927471.60
      1955924.94     13927456.56      1955925.00     13927425.00

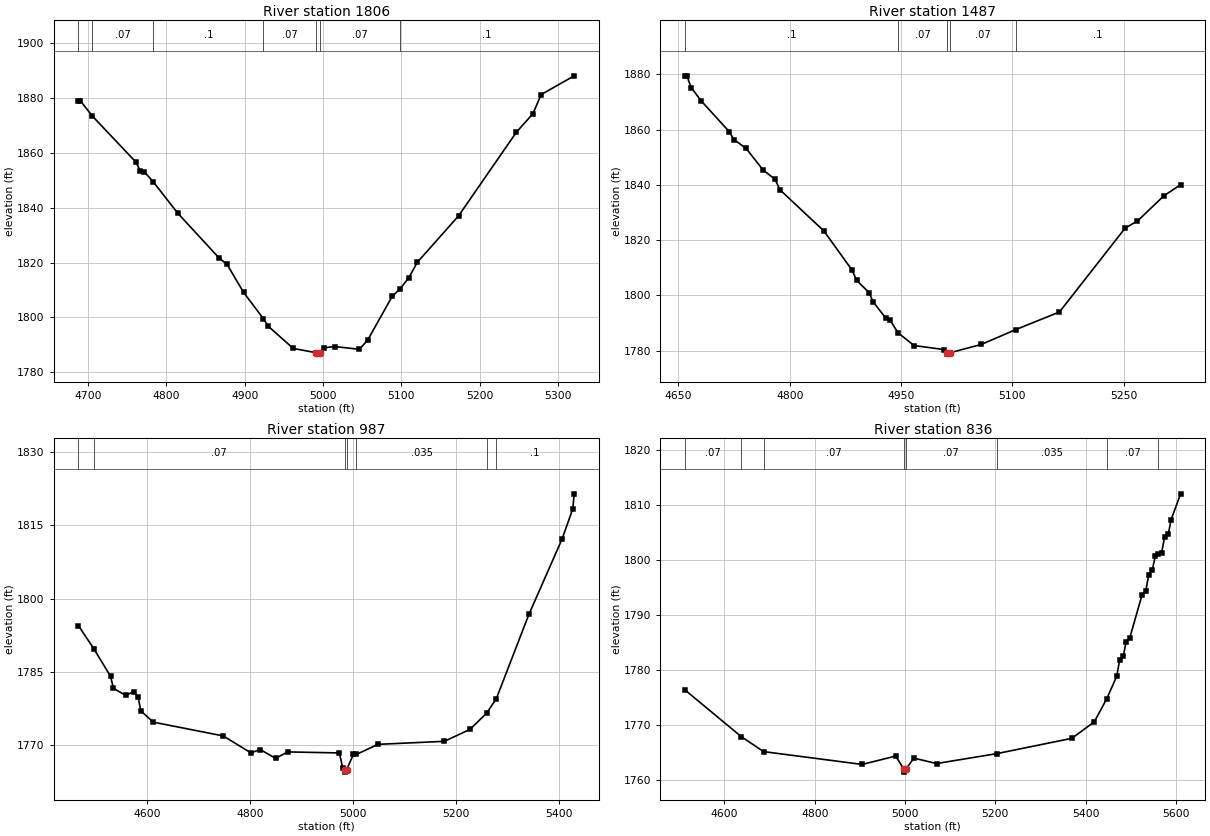
Type RM Length L Ch R = 1,1806,319,319,319
BEGIN DESCRIPTION:
Stream0017 3.0
END DESCRIPTION:
XS GIS Cut Line= 3
      1954925.01     13926625.00      1955225.00     13926525.00
      1955524.95     13926425.02
#Sta/Elev= 30
  4687.9 1878.94  4690.5 1878.94  4705.6 1873.41  4761.7 1856.48  4766.9 1853.27
  4772.2 1853.00  4783.6 1849.36  4814.4 1838.08  4867.1 1821.77  4877.6 1819.33
  4898.7 1809.13  4923.8 1799.61  4930.3 1796.77  4962.0 1788.73  4991.6 1787.16
  4991.8 1786.66  4995.6 1787.16  5001.5 1789.00  5014.7 1789.42  5046.3 1788.43
  5056.8 1791.71  5088.4 1807.79  5098.6 1810.54  5109.5 1814.51  5120.1 1820.05
  5172.8 1836.99  5246.6 1867.47  5267.6 1874.17  5278.2 1881.18  5320.3 1888.01
#Mann=7,-1,0
  4687.9     0.1       0  4705.6    0.07       0  4783.6     0.1       0
  4923.8    0.07       0  4991.6    0.05       0  4995.6    0.07       0
  5098.6     0.1       0
Bank Sta=4991.6,4995.6
Exp/Cntr=0.3,0.1

Type RM Length L Ch R = 1,1487,500,500,500
BEGIN DESCRIPTION:
Stream0017 2.0
END DESCRIPTION:
XS GIS Cut Line= 3
      1954925.03     13926675.01      1955240.11     13926822.08
      1955524.97     13926675.02
#Sta/Elev= 30
  4658.5 1879.49  4661.2 1879.49  4667.1 1875.24  4680.5 1870.45  4718.4 1859.27
  4724.7 1856.43  4741.2 1853.20  4764.1 1845.37  4779.9 1842.09  4786.9 1838.19
  4846.1 1823.29  4883.9 1809.16  4890.2 1805.40  4906.8 1801.04  4912.3 1797.68
  4929.6 1791.70  4935.1 1791.06  4945.9 1786.47  4967.5 1781.84  5008.5 1780.36
  5012.0 1779.23  5012.3 1778.73  5016.0 1779.23  5058.4 1782.26  5104.5 1787.60
  5163.5 1793.99  5252.1 1824.39  5268.6 1826.91  5304.3 1836.08  5326.8 1840.06
#Mann=5,-1,0
  4658.5     0.1       0  4945.9    0.07       0  5012.0    0.05       0
  5016.0    0.07       0  5104.5     0.1       0
Bank Sta=5012,5016
Exp/Cntr=0.3,0.1

Type RM Length L Ch R = 1,987,151,151,151
BEGIN DESCRIPTION:
Stream0017 1.0
END DESCRIPTION:
XS GIS Cut Line= 3
      1954775.00     13927075.00      1955270.44     13927277.37
      1955613.41     13927019.47
#Sta/Elev= 30
  4465.9 1794.51  4496.1 1789.74  4528.7 1784.08  4534.1 1781.65  4558.1 1780.19
  4573.9 1780.98  4582.1 1779.85  4587.5 1777.03  4611.5 1774.72  4747.9 1771.89
  4801.3 1768.44  4819.9 1769.09  4849.4 1767.31  4873.4 1768.62  4973.6 1768.41
  4980.3 1765.23  4983.7 1764.98  4983.9 1764.48  4987.7 1764.98  5000.8 1768.10
  5006.6 1768.10  5048.6 1770.17  5177.7 1770.79  5227.7 1773.24  5259.8 1776.55
  5278.7 1779.49  5342.2 1796.79  5406.8 1812.25  5427.6 1818.43  5430.2 1821.48
#Mann=7,-1,0
  4465.9     0.1       0  4496.1    0.07       0  4983.7    0.05       0
  4987.7    0.07       0  5006.6   0.035       0  5259.8    0.07       0
  5278.7     0.1       0
Bank Sta=4983.7,4987.7
Exp/Cntr=0.3,0.1

Type RM Length L Ch R = 1,836,0,0,0
BEGIN DESCRIPTION:
Stream0017 0.0
END DESCRIPTION:
XS GIS Cut Line= 4
      1954859.16     13927144.40      1955115.33     13927421.34
      1955352.10     13927401.67      1955733.25     13927104.40
#Sta/Elev= 30
  4512.2 1776.42  4637.2 1767.91  4686.7 1765.18  4904.9 1762.85  4979.4 1764.37
  4997.5 1761.95  4997.7 1761.45  5001.5 1761.95  5019.6 1764.00  5069.7 1763.01
  5203.1 1764.81  5369.5 1767.60  5419.2 1770.60  5447.0 1774.83  5469.0 1778.91
  5475.3 1781.83  5483.5 1782.58  5489.8 1785.18  5497.9 1785.90  5525.1 1793.73
  5533.2 1794.37  5539.6 1797.34  5547.7 1798.20  5554.0 1800.69  5560.8 1801.18
  5568.2 1801.35  5574.8 1804.17  5583.0 1804.67  5589.3 1807.37  5610.4 1812.06
#Mann=8,-1,0
  4512.2    0.07       0  4637.2   0.035       0  4686.7    0.07       0
  4997.5    0.05       0  5001.5    0.07       0  5203.1   0.035       0
  5447.0    0.07       0  5560.8     0.1       0
Bank Sta=4997.5,5001.5
Exp/Cntr=0.3,0.1

Chan Stop Cuts=-1