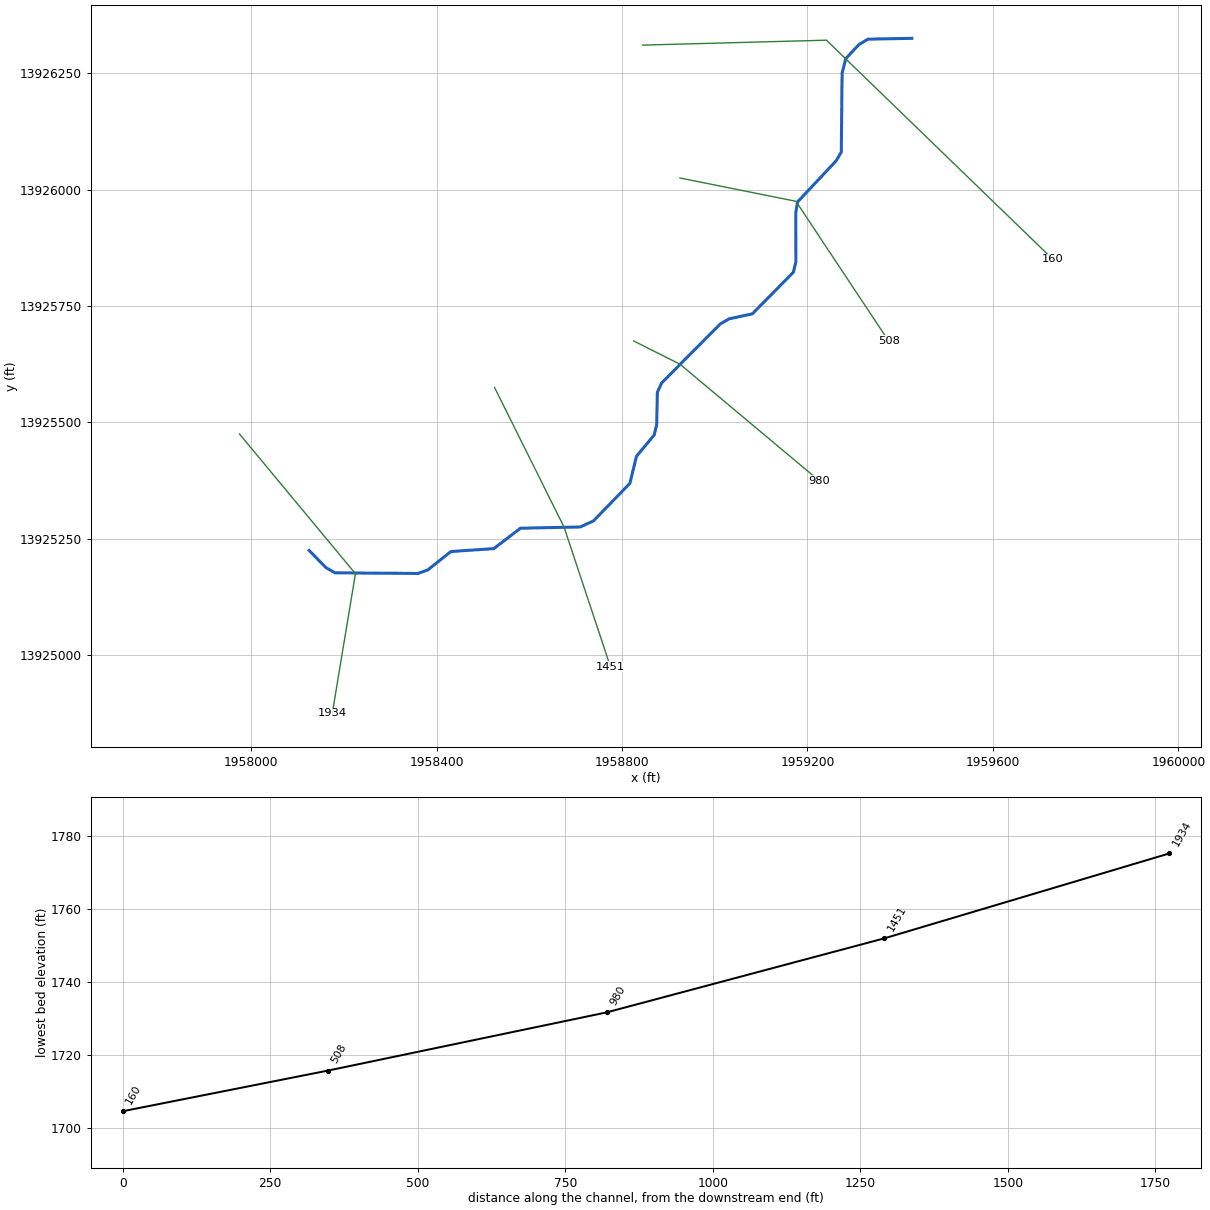
--- Stream0018.prj (project) ---

Proj Title=Stream0018 Base Level Engineering
Current Plan=p01
Default Exp/Contr=0.3,0.1
English Units
Geom File=g01
Flow File=f01
Plan File=p01
BEGIN DESCRIPTION:
Stream0018
END DESCRIPTION:

--- Stream0018.p01 (plan) ---

Plan Title=Multiple Run
Short Identifier=Multiple
Geom File=g01
Flow File=f01
Subcritical Flow
K Sum by GR= 0
Std Step Tol= 0.01
Critical Tol= 0.01
Num of Std Step Trials= 20
Max Error Tol= 0.3
Flow Tol Ratio= 0.001
Split Flow NTrial= 30
Split Flow Tol= 0.02
Split Flow Ratio= 0.02
Log Output Level= 0
Friction Slope Method= 1
Unsteady Friction Slope Method= 2
Unsteady Bridges Friction Slope Method= 1
Parabolic Critical Depth
Global Vel Dist=  1 , 1 , 1
Global Log Level= 0
CheckData=True
Encroach Param= -1, 0, 0, 0
BEGIN DESCRIPTION:
Multiple Run
END DESCRIPTION:

--- Stream0018.f01 (steady flow) ---

Flow Title=Multiple
Number of Profiles=7
Profile Names=10-year,25-year,50-year,1pct_min,100-year,1pct_plu,500-year
River Rch & RM= Stream0018,Reach-1,1934
     585     958    1302     860    1716    3423    2929
Boundary for River Rch & Prof#=Stream0018,Reach-1,1
Up Type=0
Dn Type=3
Dn Slope=0.005
Boundary for River Rch & Prof#=Stream0018,Reach-1,2
Up Type=0
Dn Type=3
Dn Slope=0.005
Boundary for River Rch & Prof#=Stream0018,Reach-1,3
Up Type=0
Dn Type=3
Dn Slope=0.005
Boundary for River Rch & Prof#=Stream0018,Reach-1,4
Up Type=0
Dn Type=3
Dn Slope=0.005
Boundary for River Rch & Prof#=Stream0018,Reach-1,5
Up Type=0
Dn Type=3
Dn Slope=0.005
Boundary for River Rch & Prof#=Stream0018,Reach-1,6
Up Type=0
Dn Type=3
Dn Slope=0.005
Boundary for River Rch & Prof#=Stream0018,Reach-1,7
Up Type=0
Dn Type=3
Dn Slope=0.005

--- Stream0018.g01 (geometry) ---

Geom Title=Existing Conditions

River Reach=Stream0018,Reach-1
Reach XY= 30
      1958125.00     13925225.00      1958161.50     13925187.92
      1958180.78     13925176.89      1958359.78     13925175.52
      1958381.06     13925183.14      1958430.98     13925222.64
      1958523.40     13925228.86      1958580.94     13925272.73
      1958709.84     13925275.39      1958738.34     13925288.36
      1958816.87     13925368.92      1958831.14     13925427.17
      1958869.23     13925472.68      1958874.76     13925495.10
      1958876.16     13925564.52      1958885.52     13925584.79
      1959011.79     13925711.37      1959031.05     13925722.46
      1959081.07     13925733.15      1959169.54     13925822.54
      1959175.02     13925844.99      1959174.73     13925950.11
      1959178.56     13925973.53      1959261.60     13926061.69
      1959272.93     13926080.86      1959274.67     13926250.21
      1959282.65     13926281.52      1959311.20     13926311.84
      1959330.52     13926323.24      1959425.00     13926325.00

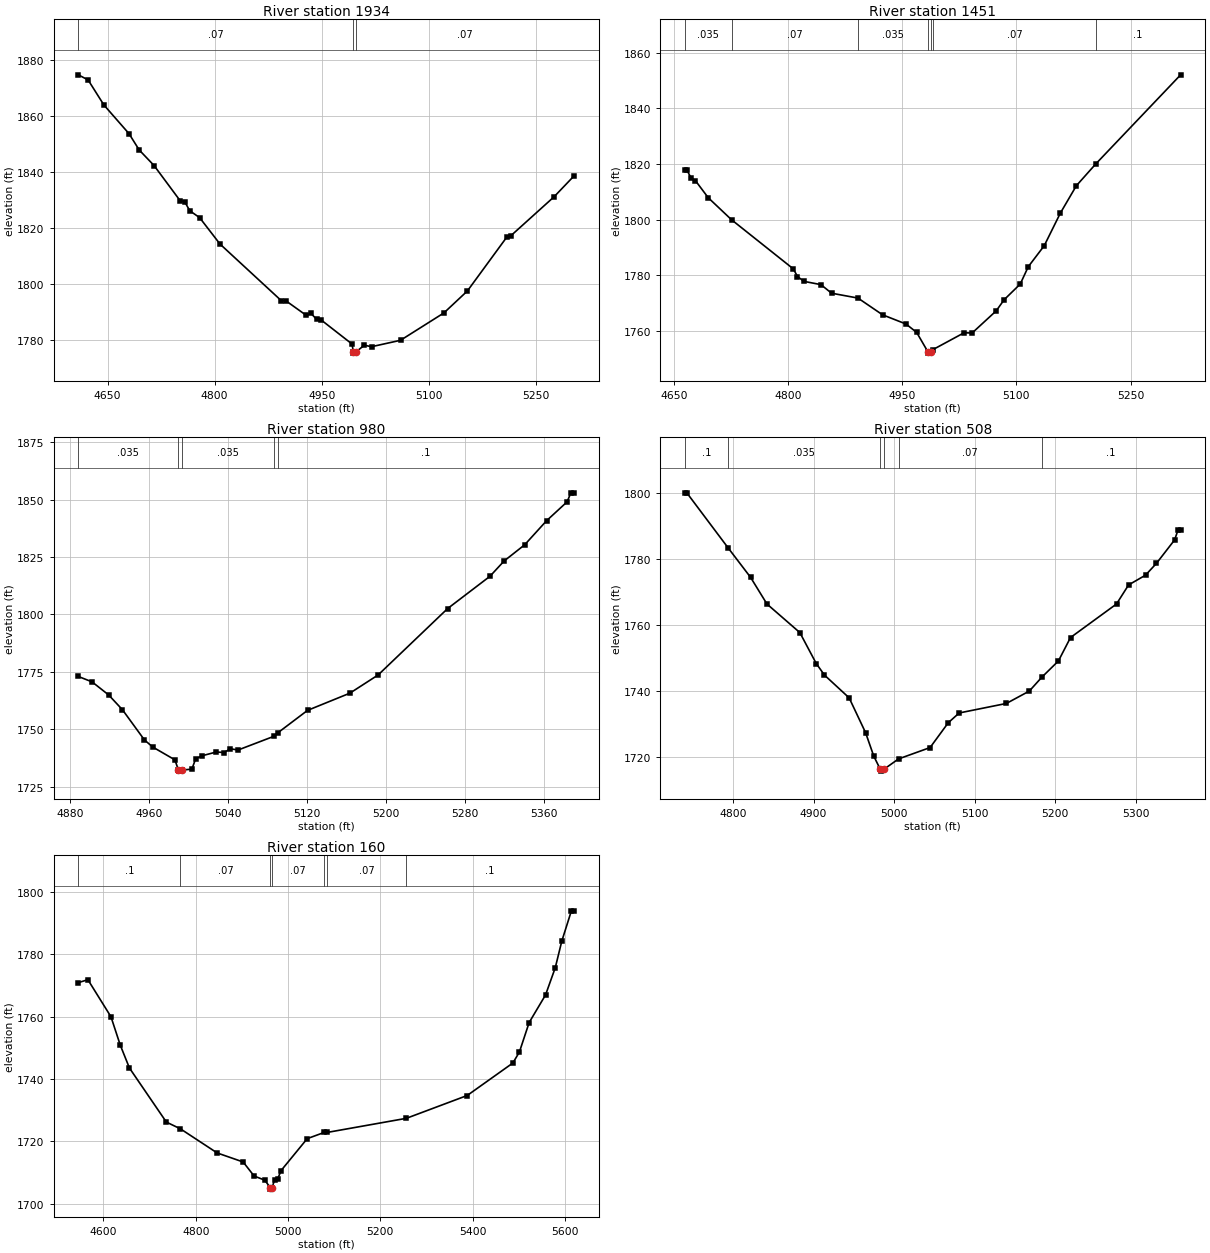
Type RM Length L Ch R = 1,1934,483,483,483
BEGIN DESCRIPTION:
Stream0018 4.0
END DESCRIPTION:
XS GIS Cut Line= 3
      1957974.98     13925475.02      1958225.00     13925175.00
      1958175.00     13924874.98
#Sta/Elev= 30
  4609.1 1874.83  4622.8 1873.00  4644.9 1864.05  4680.1 1853.78  4694.4 1847.94
  4715.2 1842.38  4751.7 1829.81  4758.2 1829.38  4765.3 1826.19  4779.0 1823.75
  4807.6 1814.29  4893.6 1794.01  4900.1 1793.96  4928.7 1788.74  4935.2 1789.45
  4943.0 1787.35  4949.5 1787.10  4992.5 1778.54  4994.4 1775.77  4994.6 1775.27
  4998.4 1775.77  5009.8 1778.10  5019.9 1777.57  5060.5 1779.86  5121.3 1789.65
  5154.2 1797.51  5210.0 1816.98  5215.1 1817.26  5275.9 1831.26  5303.8 1838.72
#Mann=3,-1,0
  4609.1    0.07       0  4994.4    0.05       0  4998.4    0.07       0
Bank Sta=4994.4,4998.4
Exp/Cntr=0.3,0.1

Type RM Length L Ch R = 1,1451,471,471,471
BEGIN DESCRIPTION:
Stream0018 3.0
END DESCRIPTION:
XS GIS Cut Line= 3
      1958525.00     13925575.01      1958675.00     13925275.00
      1958774.99     13924975.04
#Sta/Elev= 30
  4664.2 1817.75  4667.0 1817.75  4672.6 1814.86  4678.2 1813.98  4695.0 1807.85
  4725.7 1799.92  4806.8 1782.28  4812.3 1779.54  4820.7 1777.80  4843.1 1776.62
  4857.1 1773.54  4891.8 1771.79  4924.1 1765.78  4954.9 1762.47  4968.9 1759.46
  4983.6 1752.51  4983.9 1752.01  4987.6 1752.51  4990.4 1753.29  5031.2 1759.32
  5041.8 1759.24  5073.4 1767.19  5083.9 1771.21  5105.0 1776.82  5115.6 1783.07
  5136.6 1790.63  5157.7 1802.30  5178.8 1812.17  5204.1 1819.94  5315.8 1852.01
#Mann=7,-1,0
  4664.2   0.035       0  4725.7    0.07       0  4891.8   0.035       0
  4983.6    0.05       0  4987.6   0.035       0  4990.4    0.07       0
  5204.1     0.1       0
Bank Sta=4983.6,4987.6
Exp/Cntr=0.3,0.1

Type RM Length L Ch R = 1,980,472,472,472
BEGIN DESCRIPTION:
Stream0018 2.0
END DESCRIPTION:
XS GIS Cut Line= 3
      1958825.03     13925674.99      1958925.00     13925625.00
      1959225.01     13925374.99
#Sta/Elev= 30
  4888.5 1772.93  4902.4 1770.59  4919.2 1764.89  4933.2 1758.44  4955.5 1745.27
  4963.9 1742.20  4986.3 1736.63  4989.9 1732.21  4990.1 1731.71  4993.9 1732.21
  5003.5 1732.56  5007.4 1737.10  5013.9 1738.41  5028.3 1740.04  5036.1 1739.82
  5042.6 1741.43  5050.4 1740.92  5086.9 1746.92  5090.7 1748.43  5120.7 1758.17
  5163.6 1765.66  5192.3 1773.62  5262.6 1802.50  5305.5 1816.56  5319.8 1823.21
  5340.7 1830.29  5362.8 1840.74  5383.6 1848.97  5387.5 1852.91  5390.8 1852.91
#Mann=5,-1,0
  4888.5   0.035       0  4989.9   0.035       0  4993.9   0.035       0
  5086.9    0.07       0  5090.7     0.1       0
Bank Sta=4989.9,4993.9
Exp/Cntr=0.3,0.1

Type RM Length L Ch R = 1,508,348,348,348
BEGIN DESCRIPTION:
Stream0018 1.0
END DESCRIPTION:
XS GIS Cut Line= 3
      1958925.00     13926025.00      1959175.00     13925975.00
      1959375.00     13925675.00
#Sta/Elev= 30
  4740.2 1800.20  4742.7 1800.20  4793.7 1783.59  4821.8 1774.58  4842.2 1766.47
  4883.0 1757.81  4903.4 1748.41  4913.6 1744.91  4944.2 1738.01  4964.6 1727.46
  4974.8 1720.31  4983.0 1716.28  4983.2 1715.78  4987.0 1716.28  5005.5 1719.48
  5044.7 1722.93  5067.3 1730.47  5080.8 1733.42  5139.4 1736.31  5167.9 1740.07
  5183.4 1744.27  5204.0 1749.20  5219.0 1756.30  5276.1 1766.48  5291.1 1772.26
  5312.1 1775.22  5325.7 1778.81  5348.2 1785.91  5352.7 1789.07  5355.7 1789.07
#Mann=6,-1,0
  4740.2     0.1       0  4793.7   0.035       0  4983.0   0.035       0
  4987.0   0.035       0  5005.5    0.07       0  5183.4     0.1       0
Bank Sta=4983,4987
Exp/Cntr=0.3,0.1

Type RM Length L Ch R = 1,160,0,0,0
BEGIN DESCRIPTION:
Stream0018 0.0
END DESCRIPTION:
XS GIS Cut Line= 3
      1958844.33     13926310.45      1959240.91     13926321.02
      1959728.68     13925850.84
#Sta/Elev= 30
  4545.7 1770.91  4566.4 1771.85  4616.4 1759.95  4636.4 1750.91  4656.4 1743.51
  4736.4 1726.16  4767.0 1723.98  4846.5 1716.25  4902.8 1713.35  4926.5 1708.85
  4949.5 1707.52  4961.6 1705.14  4961.9 1704.64  4965.6 1705.14  4970.8 1707.63
  4977.8 1708.01  4985.0 1710.61  5041.6 1720.84  5078.5 1722.84  5084.6 1722.83
  5256.3 1727.36  5388.1 1734.68  5487.1 1745.11  5501.3 1748.65  5522.4 1758.11
  5557.9 1766.95  5579.0 1775.71  5593.1 1784.22  5613.9 1793.95  5619.9 1793.95
#Mann=7,-1,0
  4545.7     0.1       0  4767.0    0.07       0  4961.6    0.05       0
  4965.6    0.07       0  5078.5     0.1       0  5084.6    0.07       0
  5256.3     0.1       0
Bank Sta=4961.6,4965.6
Exp/Cntr=0.3,0.1

Chan Stop Cuts=-1