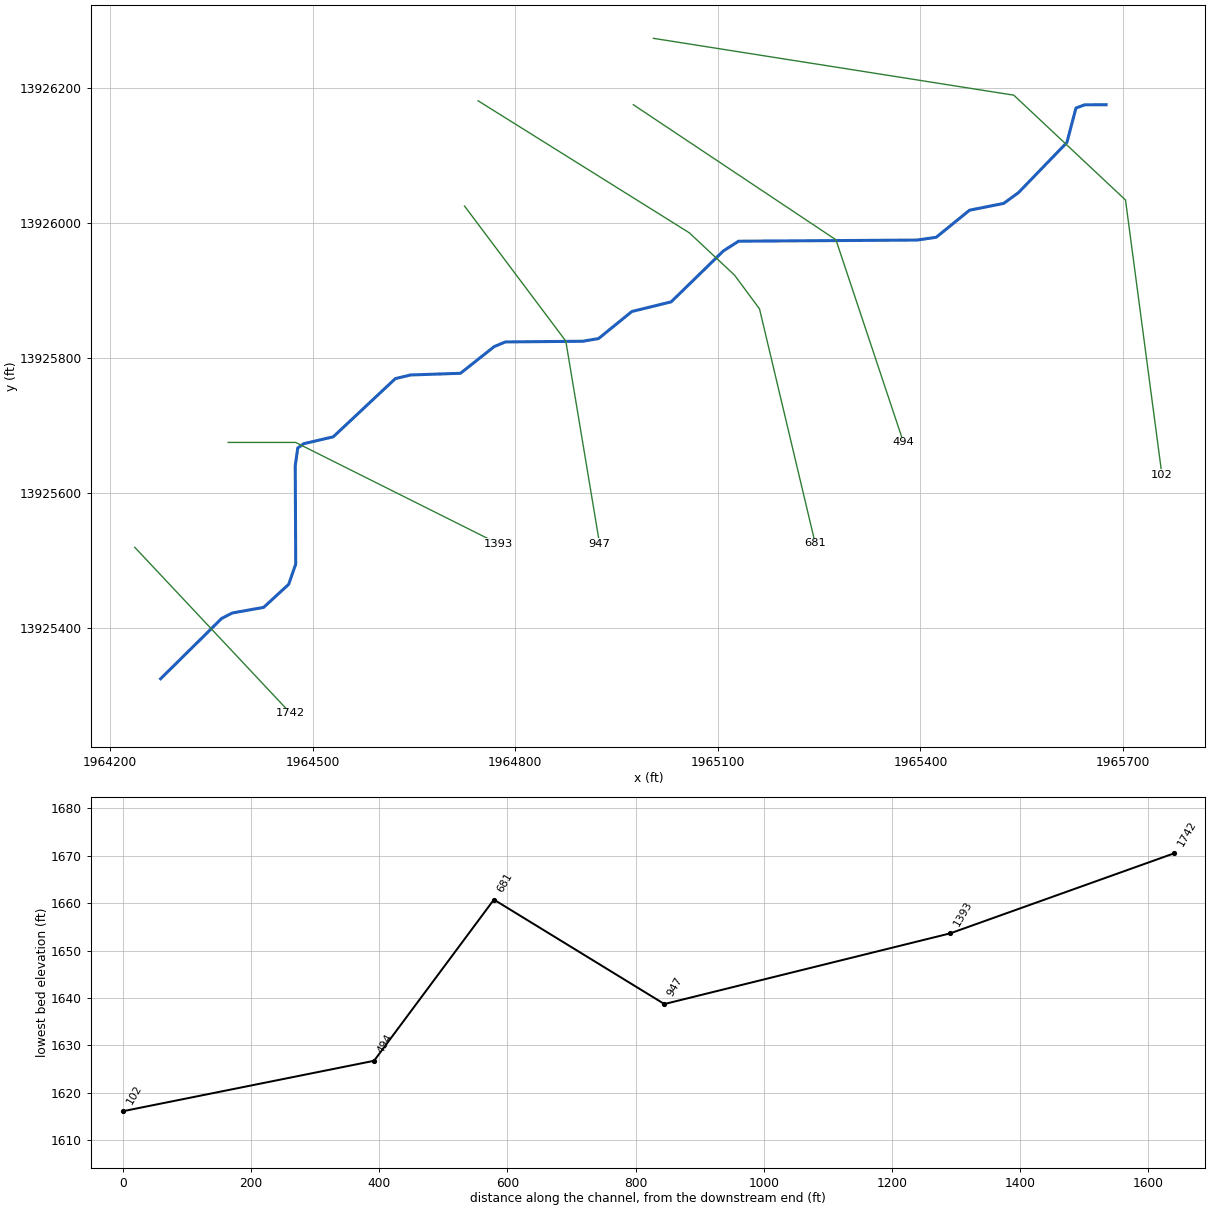
--- Stream0020.prj (project) ---

Proj Title=Stream0020 Base Level Engineering
Current Plan=p01
Default Exp/Contr=0.3,0.1
English Units
Geom File=g01
Flow File=f01
Plan File=p01
Y Axis Title=Elevation
X Axis Title(PF)=Main Channel Distance
X Axis Title(XS)=Station
BEGIN DESCRIPTION:
Stream0020
END DESCRIPTION:
DSS Export Rating Curves= 0
DSS Export Rating Curve Sorted= 0
DSS Export Volume Flow Curves= 0
DXF OffsetX= 0
DXF OffsetY= 0
DXF ScaleX= 1
DXF ScaleY= 10

--- Stream0020.p01 (plan) ---

Plan Title=Multiple Run
Short Identifier=Multiple
Geom File=g01
Flow File=f01
Subcritical Flow
K Sum by GR= 0
Std Step Tol= 0.01
Critical Tol= 0.01
Num of Std Step Trials= 20
Max Error Tol= 0.3
Flow Tol Ratio= 0.001
Split Flow NTrial= 30
Split Flow Tol= 0.02
Split Flow Ratio= 0.02
Log Output Level= 0
Friction Slope Method= 1
Unsteady Friction Slope Method= 2
Unsteady Bridges Friction Slope Method= 1
Parabolic Critical Depth
Global Vel Dist=  1 , 1 , 1
Global Log Level= 0
CheckData=True
Encroach Param= -1, 0, 0, 0
BEGIN DESCRIPTION:
Multiple Run
END DESCRIPTION:

--- Stream0020.f01 (steady flow) ---

Flow Title=Multiple
Number of Profiles=7
Profile Names=10-year,25-year,50-year,1pct_min,100-year,1pct_plu,500-year
River Rch & RM= Stream0020,Reach-1,1742
     698    1161    1594    1062    2120    4230    3691
Boundary for River Rch & Prof#=Stream0020,Reach-1,1
Up Type=0
Dn Type=3
Dn Slope=0.005
Boundary for River Rch & Prof#=Stream0020,Reach-1,2
Up Type=0
Dn Type=3
Dn Slope=0.005
Boundary for River Rch & Prof#=Stream0020,Reach-1,3
Up Type=0
Dn Type=3
Dn Slope=0.005
Boundary for River Rch & Prof#=Stream0020,Reach-1,4
Up Type=0
Dn Type=3
Dn Slope=0.005
Boundary for River Rch & Prof#=Stream0020,Reach-1,5
Up Type=0
Dn Type=3
Dn Slope=0.005
Boundary for River Rch & Prof#=Stream0020,Reach-1,6
Up Type=0
Dn Type=3
Dn Slope=0.005
Boundary for River Rch & Prof#=Stream0020,Reach-1,7
Up Type=0
Dn Type=3
Dn Slope=0.005

--- Stream0020.g01 (geometry) ---

Geom Title=Existing Conditions
Program Version=4.10

River Reach=Stream0020      ,Reach-1
Reach XY= 30
        1964275.       13925325.      1964365.31     13925414.28
      1964381.09     13925422.46      1964427.58     13925430.73
      1964464.66     13925464.88      1964475.08     13925494.88
      1964474.37     13925640.55      1964478.07      13925666.7
      1964486.69     13925673.02      1964530.69     13925683.32
      1964622.58     13925769.46      1964645.05     13925774.87
      1964719.02     13925777.36      1964768.94     13925816.86
      1964785.51     13925823.77      1964900.08     13925824.81
      1964923.44     13925828.76      1964972.83     13925868.86
      1965031.05     13925883.16      1965108.25     13925958.54
      1965130.86     13925972.94      1965395.15     13925974.64
      1965423.45     13925978.75      1965472.83     13926018.86
      1965523.38     13926028.94      1965545.13     13926044.77
      1965616.95     13926119.08      1965630.33     13926170.08
      1965643.46     13926174.93        1965675.       13926175.

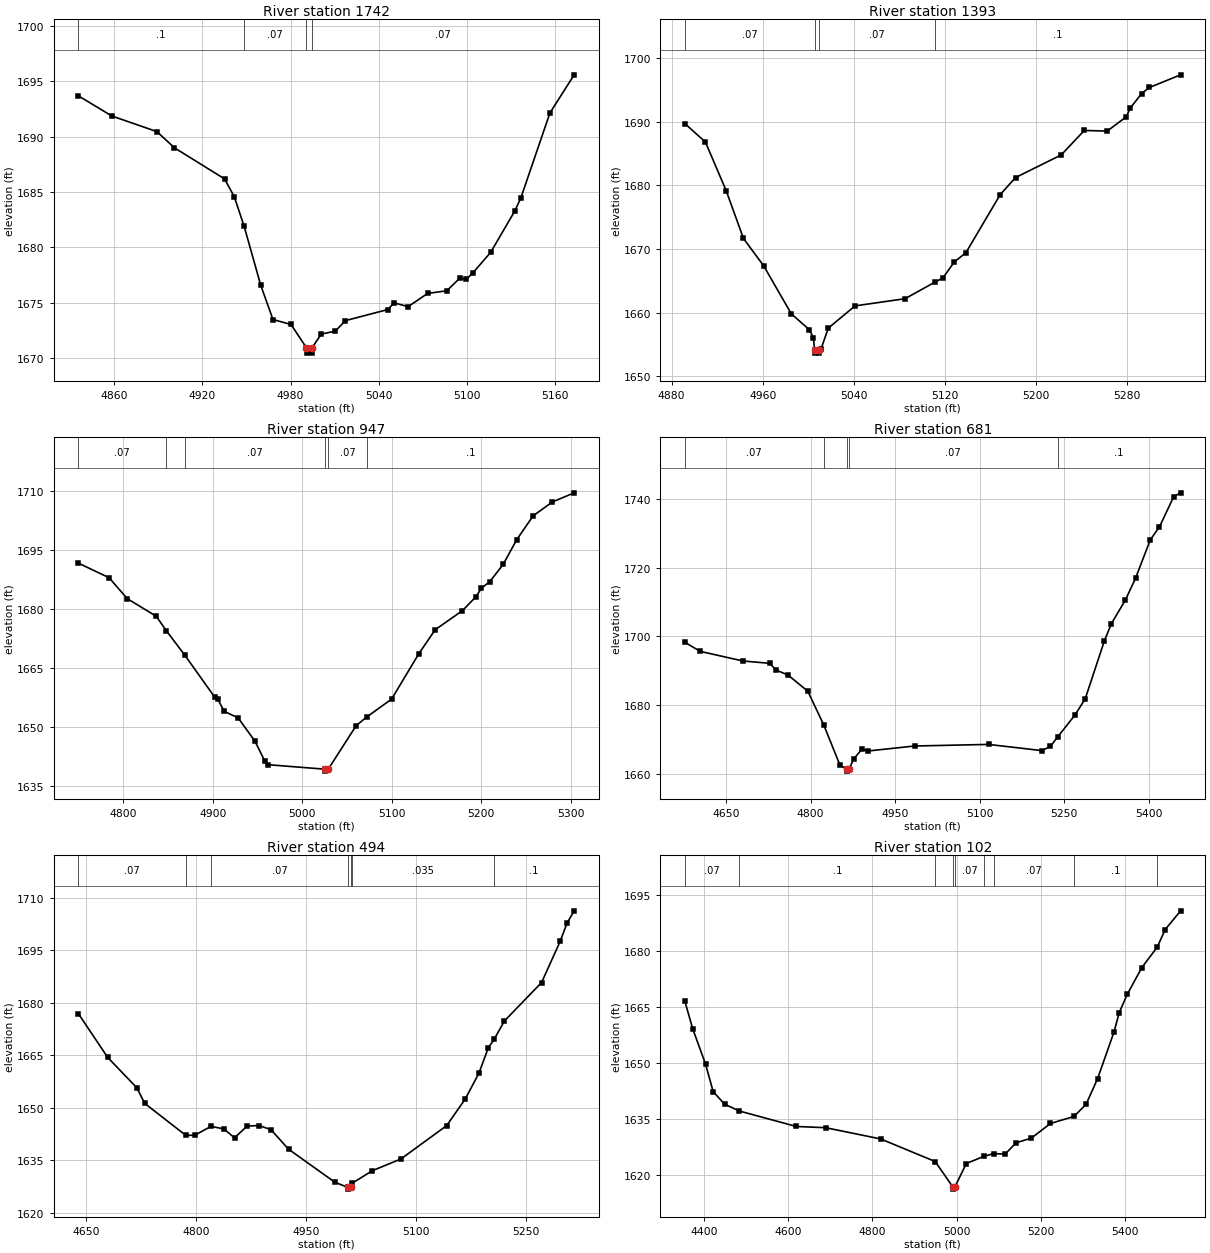
Type RM Length L Ch R = 1 ,1742    ,349,349,349
BEGIN DESCRIPTION:
Stream0020 4.0
END DESCRIPTION:
XS GIS Cut Line= 2
      1964236.74     13925519.73       1964467.6     13925273.81
#Sta/Elev= 30
  4835.6 1693.67  4858.4 1691.85  4889.1 1690.44    4901 1688.98  4935.1 1686.18
  4941.7 1684.57  4948.4 1681.91  4959.7 1676.59    4968 1673.51  4980.3 1673.06
  4990.7 1670.98  4990.9 1670.48  4994.4 1670.48  4994.7 1670.98  5000.9  1672.2
  5010.4 1672.46  5017.3 1673.41  5046.2 1674.41  5050.3 1675.01    5060 1674.67
  5073.2 1675.86  5086.3  1676.1  5095.1 1677.24  5099.5 1677.13  5103.8 1677.68
  5116.1 1679.56  5132.6 1683.31  5136.7 1684.49  5156.4 1692.12  5172.9 1695.56
#Mann= 4 ,-1 , 0
  4835.6      .1       0  4948.4     .07       0  4990.7     .05       0
  4994.7     .07       0
Bank Sta=4990.7,4994.7
XS Rating Curve= 0 ,0
Exp/Cntr=0.3,0.1

Type RM Length L Ch R = 1 ,1393    ,446,446,446
BEGIN DESCRIPTION:
Stream0020 3.0
END DESCRIPTION:
XS GIS Cut Line= 3
      1964375.04       13925675.        1964475.       13925675.
      1964775.03     13925524.99
#Sta/Elev= 30
  4891.6 1689.74  4909.7 1686.83  4927.9  1679.2  4943.1 1671.67  4960.9 1667.35
  4985.1 1659.82  5000.9 1657.32  5004.5 1656.07  5005.6 1654.13  5005.8 1653.63
  5009.3 1653.63  5009.6 1654.13  5011.2 1654.26  5017.6 1657.56  5041.1 1661.06
    5085 1662.19  5111.3  1664.8  5118.3 1665.46  5128.3 1667.98  5138.4 1669.41
  5168.6 1678.57    5182 1681.24  5222.2 1684.81  5242.4 1688.65  5262.5 1688.55
  5279.3  1690.8  5282.6 1692.13  5292.7 1694.45  5299.6 1695.41    5327  1697.4
#Mann= 4 ,-1 , 0
  4891.6     .07       0  5005.6     .05       0  5009.6     .07       0
  5111.3      .1       0
Bank Sta=5005.6,5009.6
XS Rating Curve= 0 ,0
Exp/Cntr=0.3,0.1

Type RM Length L Ch R = 1 ,947     ,266,266,266
BEGIN DESCRIPTION:
Stream0020 2.0
END DESCRIPTION:
XS GIS Cut Line= 3
      1964725.01     13926024.98        1964875.       13925825.
        1964925.     13925525.02
#Sta/Elev= 30
  4749.7 1691.67    4784 1687.96  4804.4 1682.63  4836.9 1678.12  4847.9 1674.51
  4868.9 1668.17  4901.9 1657.62  4905.7 1657.01  4912.6 1653.96  4928.2 1652.29
  4946.9 1646.43  4958.2 1641.24  4961.9 1640.36    5025 1639.23  5025.2 1638.73
    5029 1639.23  5060.3 1650.34  5072.7 1652.62  5099.8 1657.07  5130.2 1668.61
  5148.5 1674.72  5178.9 1679.57  5194.1 1683.12  5200.2  1685.3  5209.5 1686.95
  5224.5 1691.35  5239.7 1697.67    5258 1703.71  5279.3 1707.21  5303.8 1709.56
#Mann= 6 ,-1 , 0
  4749.7     .07       0  4847.9      .1       0  4868.9     .07       0
    5025     .05       0    5029     .07       0  5072.7      .1       0
Bank Sta=5025,5029
XS Rating Curve= 0 ,0
Exp/Cntr=0.3,0.1

Type RM Length L Ch R = 1 ,681     ,187,187,187
BEGIN DESCRIPTION:
Stream0020 1.1
END DESCRIPTION:
XS GIS Cut Line= 5
      1964745.15     13926180.85      1965057.66     13925985.53
      1965124.93      13925922.6      1965161.82     13925872.68
      1965244.29     13925525.46
#Sta/Elev= 30
  4576.8 1698.28  4604.1 1695.63  4679.7 1692.83  4727.6 1692.14  4738.4 1690.21
  4759.8 1688.74    4795 1684.02  4823.3  1674.2  4851.8 1662.59  4863.9 1661.24
  4864.2 1660.74  4867.9 1661.24  4876.5 1664.28  4891.2 1667.19  4901.3  1666.6
  4984.6 1668.06  5115.6 1668.52    5210 1666.72  5225.4 1667.92  5238.2  1670.7
  5268.6 1677.01  5287.1 1681.77    5321 1698.62  5333.3 1703.62  5358.3 1710.56
  5376.5 1716.95  5402.6 1728.12  5418.9 1731.92  5444.3 1740.73  5456.4 1741.81
#Mann= 5 ,-1 , 0
  4576.8     .07       0  4823.3     .07       0  4863.9     .05       0
  4867.9     .07       0  5238.2      .1       0
Bank Sta=4863.9,4867.9
XS Rating Curve= 0 ,0
Exp/Cntr=0.3,0.1

Type RM Length L Ch R = 1 ,494     ,392,392,392
BEGIN DESCRIPTION:
Stream0020 1.0
END DESCRIPTION:
XS GIS Cut Line= 3
      1964974.96     13926175.03        1965275.       13925975.
      1965374.99     13925675.03
#Sta/Elev= 30
  4639.4 1676.89  4679.5 1664.37  4719.2 1655.71    4730 1651.25  4786.2  1642.1
  4798.5 1642.17  4820.5 1644.69  4838.1 1643.95  4852.6 1641.42  4869.8 1644.77
    4886 1644.93  4902.3 1643.76  4926.3 1638.18  4989.6 1628.73  5007.3 1627.27
  5007.5 1626.77  5011.3 1627.27  5013.6 1628.52  5040.9 1632.04  5079.8 1635.39
  5142.1 1644.89  5167.4 1652.45  5186.3 1659.91    5199 1667.11    5207 1669.57
  5221.1  1674.8  5271.7 1685.74    5297 1697.47  5306.5 1702.71  5316.2 1706.22
#Mann= 7 ,-1 , 0
  4639.4     .07       0  4786.2      .1       0  4820.5     .07       0
  5007.3     .05       0  5011.3     .07       0  5013.6    .035       0
    5207      .1       0
Bank Sta=5007.3,5011.3
XS Rating Curve= 0 ,0
Exp/Cntr=0.3,0.1

Type RM Length L Ch R = 1 ,102     ,0,0,0
BEGIN DESCRIPTION:
Stream0020 0.0
END DESCRIPTION:
XS GIS Cut Line= 4
      1965004.74     13926273.32      1965538.27     13926189.18
      1965703.73     13926033.92      1965757.69      13925626.7
#Sta/Elev= 30
  4354.2 1666.51    4373 1659.08  4403.4 1649.66  4421.6 1642.24  4448.9 1638.88
  4483.8 1637.06    4619 1632.92  4688.9 1632.59  4819.5 1629.58    4949 1623.53
  4991.4 1616.64  4991.6 1616.14  4995.4 1616.64  5022.9    1623  5064.8 1624.94
  5088.3 1625.67  5114.9  1625.5  5141.1 1628.54  5177.4  1629.8  5222.8 1633.72
  5278.8 1635.61  5307.5 1638.88  5334.8 1645.73  5373.7 1658.21  5386.2 1663.43
  5405.1 1668.27  5439.9 1675.48  5476.4 1680.94  5495.2 1685.64    5532 1690.67
#Mann= 9 ,-1 , 0
  4354.2     .07       0  4483.8      .1       0    4949     .07       0
  4991.4     .05       0  4995.4     .07       0  5064.8    .035       0
  5088.3     .07       0  5278.8      .1       0  5476.4     .07       0
Bank Sta=4991.4,4995.4
XS Rating Curve= 0 ,0
Exp/Cntr=0.3,0.1

Chan Stop Cuts=-1
Use User Specified Reach Order=0
Composite Channel Slope=5