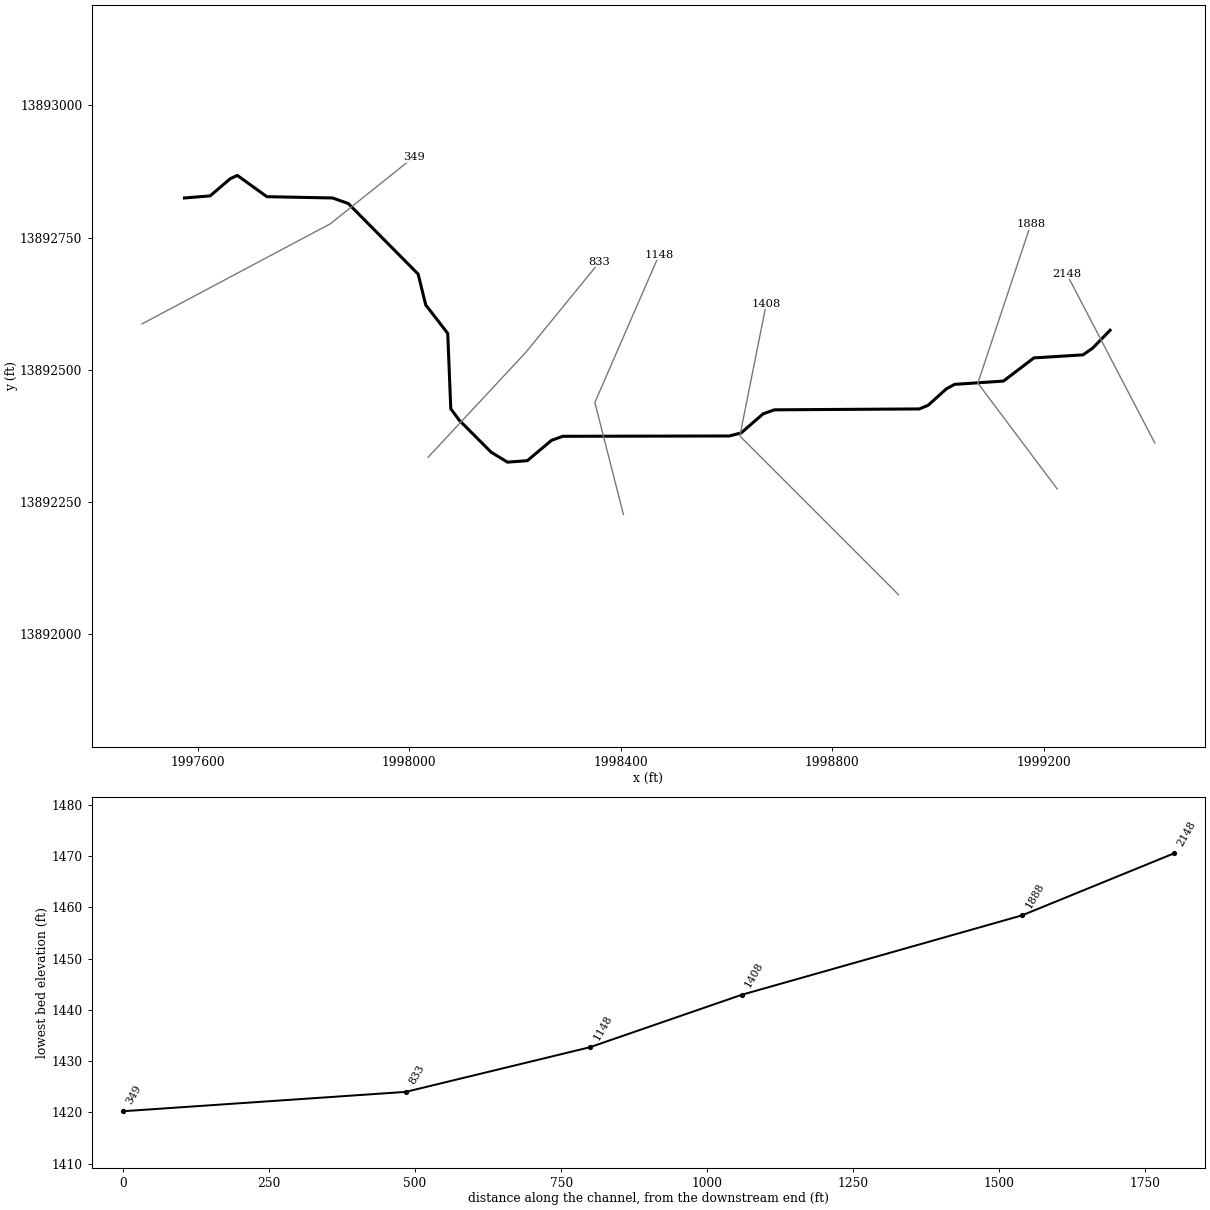
--- Stream0021.prj (project) ---

Proj Title=Stream0021 Base Level Engineering
Current Plan=p01
Default Exp/Contr=0.3,0.1
English Units
Geom File=g01
Flow File=f01
Plan File=p01
BEGIN DESCRIPTION:
Stream0021
END DESCRIPTION:

--- Stream0021.p01 (plan) ---

Plan Title=Multiple Run
Short Identifier=Multiple
Geom File=g01
Flow File=f01
Subcritical Flow
K Sum by GR= 0
Std Step Tol= 0.01
Critical Tol= 0.01
Num of Std Step Trials= 20
Max Error Tol= 0.3
Flow Tol Ratio= 0.001
Split Flow NTrial= 30
Split Flow Tol= 0.02
Split Flow Ratio= 0.02
Log Output Level= 0
Friction Slope Method= 1
Unsteady Friction Slope Method= 2
Unsteady Bridges Friction Slope Method= 1
Parabolic Critical Depth
Global Vel Dist=  1 , 1 , 1
Global Log Level= 0
CheckData=True
Encroach Param= -1, 0, 0, 0
BEGIN DESCRIPTION:
Multiple Run
END DESCRIPTION:

--- Stream0021.f01 (steady flow) ---

Flow Title=Multiple
Number of Profiles=7
Profile Names=10-year,25-year,50-year,1pct_min,100-year,1pct_plu,500-year
River Rch & RM= Stream0021,Reach-1,2148
     203     309     400     253     505    1007     792
Boundary for River Rch & Prof#=Stream0021,Reach-1,1
Up Type=0
Dn Type=3
Dn Slope=0.005
Boundary for River Rch & Prof#=Stream0021,Reach-1,2
Up Type=0
Dn Type=3
Dn Slope=0.005
Boundary for River Rch & Prof#=Stream0021,Reach-1,3
Up Type=0
Dn Type=3
Dn Slope=0.005
Boundary for River Rch & Prof#=Stream0021,Reach-1,4
Up Type=0
Dn Type=3
Dn Slope=0.005
Boundary for River Rch & Prof#=Stream0021,Reach-1,5
Up Type=0
Dn Type=3
Dn Slope=0.005
Boundary for River Rch & Prof#=Stream0021,Reach-1,6
Up Type=0
Dn Type=3
Dn Slope=0.005
Boundary for River Rch & Prof#=Stream0021,Reach-1,7
Up Type=0
Dn Type=3
Dn Slope=0.005

--- Stream0021.g01 (geometry) ---

Geom Title=Existing Conditions

River Reach=Stream0021,Reach-1
Reach XY= 30
      1999325.00     13892575.00      1999292.05     13892541.12
      1999273.60     13892528.39      1999180.96     13892522.68
      1999123.40     13892478.85      1999030.98     13892472.64
      1999015.37     13892464.11      1998981.06     13892433.14
      1998964.50     13892426.22      1998690.22     13892424.48
      1998668.94     13892416.86      1998627.33     13892380.75
      1998604.97     13892375.07      1998290.21     13892374.46
      1998268.92     13892366.81      1998223.25     13892328.34
      1998185.61     13892325.59      1998154.87     13892344.41
      1998094.59     13892404.79      1998078.54     13892426.45
      1998072.75     13892569.07      1998031.14     13892622.83
      1998016.86     13892681.06      1997884.80     13892814.52
      1997855.01     13892825.02      1997730.86     13892827.46
      1997674.96     13892867.69      1997661.72     13892861.52
      1997623.64     13892829.00      1997575.00     13892825.00

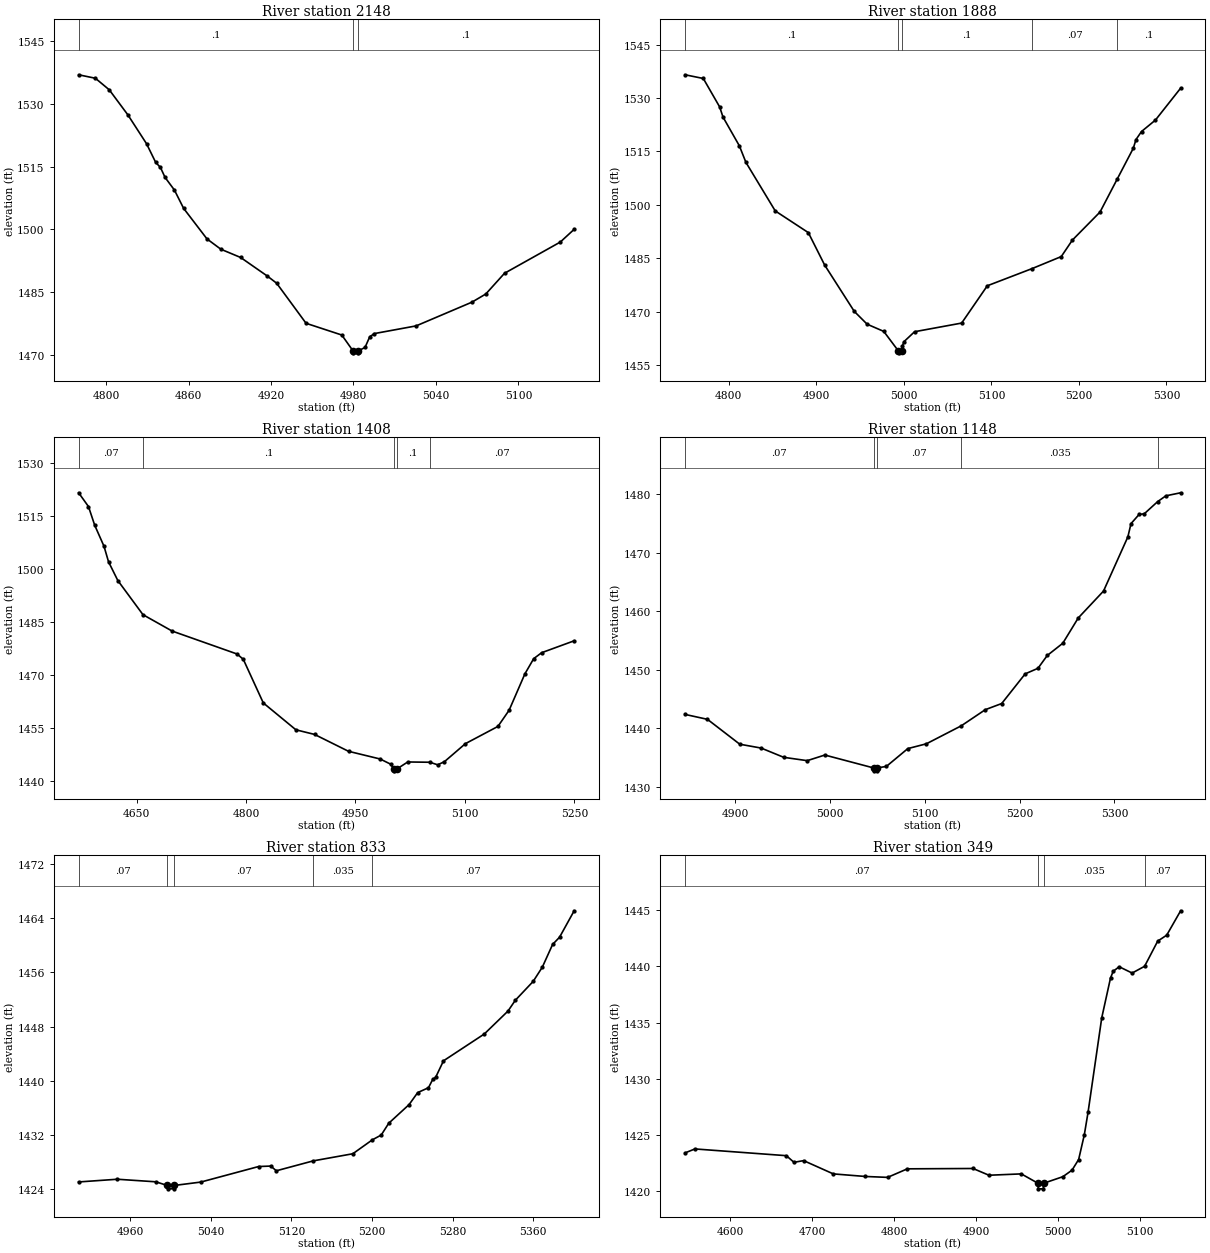
Type RM Length L Ch R = 1,2148,260,260,260
BEGIN DESCRIPTION:
Stream0021 0.3
END DESCRIPTION:
XS GIS Cut Line= 2
      1999409.48     13892361.82      1999242.83     13892681.60
#Sta/Elev= 30
  4780.0 1536.89  4792.2 1536.06  4802.3 1533.30  4815.8 1527.34  4829.4 1520.45
  4836.1 1515.97  4839.5 1514.80  4842.9 1512.40  4849.7 1509.39  4856.4 1505.02
  4873.4 1497.73  4883.5 1495.27  4897.9 1493.30  4917.3 1488.87  4924.1 1487.16
  4945.5 1477.60  4971.5 1474.80  4979.6 1471.05  4979.9 1470.55  4983.4 1470.55
  4983.6 1471.05  4988.4 1471.83  4991.8 1474.36  4995.1 1475.14  5025.6 1476.98
  5066.2 1482.64  5076.3 1484.59  5089.9 1489.53  5130.5 1496.98  5140.6 1500.02
#Mann=3,-1,0
  4780.0     0.1       0  4979.6    0.05       0  4983.6     0.1       0
Bank Sta=4979.6,4983.6
Exp/Cntr=0.3,0.1

Type RM Length L Ch R = 1,1888,480,480,480
BEGIN DESCRIPTION:
Stream0021 2.0
END DESCRIPTION:
XS GIS Cut Line= 3
      1999225.00     13892275.00      1999075.00     13892475.00
      1999174.99     13892774.97
#Sta/Elev= 30
  4750.0 1536.53  4770.8 1535.49  4789.5 1527.50  4793.3 1524.66  4812.0 1516.58
  4819.5 1511.93  4853.0 1498.30  4890.8 1492.21  4909.5 1483.08  4943.3 1470.09
  4958.0 1466.49  4977.0 1464.47  4993.8 1458.95  4994.0 1458.45  4997.8 1458.95
  4998.4 1460.41  5000.0 1461.57  5012.2 1464.38  5066.0 1466.81  5095.3 1477.28
  5146.6 1482.12  5179.8 1485.48  5192.5 1490.11  5224.1 1497.99  5243.5 1507.14
  5262.1 1515.89  5265.2 1518.35  5271.5 1520.60  5287.4 1523.81  5316.2 1532.77
#Mann=5,-1,0
  4750.0     0.1       0  4993.8    0.05       0  4997.8     0.1       0
  5146.6    0.07       0  5243.5     0.1       0
Bank Sta=4993.8,4997.8
Exp/Cntr=0.3,0.1

Type RM Length L Ch R = 1,1408,260,260,260
BEGIN DESCRIPTION:
Stream0021 1.0
END DESCRIPTION:
XS GIS Cut Line= 3
      1998924.97     13892075.03      1998625.00     13892375.00
      1998675.01     13892625.03
#Sta/Elev= 30
  4570.6 1521.63  4584.1 1517.73  4592.6 1512.46  4605.4 1506.48  4611.6 1502.09
  4624.3 1496.80  4658.8 1487.13  4698.7 1482.50  4787.8 1476.00  4796.3 1474.50
  4823.7 1462.16  4868.4 1454.55  4893.9 1453.25  4940.5 1448.47  4983.9 1446.29
  4998.2 1444.83  5002.6 1443.44  5002.9 1442.94  5006.6 1443.44  5021.7 1445.45
  5052.0 1445.37  5062.7 1444.65  5071.9 1445.52  5100.7 1450.63  5145.3 1455.51
  5160.6 1460.08  5182.3 1470.40  5194.3 1474.68  5205.2 1476.37  5249.8 1479.74
#Mann=5,-1,0
  4570.6    0.07       0  4658.8     0.1       0  5002.6    0.05       0
  5006.6     0.1       0  5052.0    0.07       0
Bank Sta=5002.6,5006.6
Exp/Cntr=0.3,0.1

Type RM Length L Ch R = 1,1148,315,315,315
BEGIN DESCRIPTION:
Stream0021 0.1
END DESCRIPTION:
XS GIS Cut Line= 3
      1998404.96     13892226.70      1998350.90     13892438.44
      1998472.51     13892717.68
#Sta/Elev= 30
  4846.8 1442.34  4870.4 1441.50  4904.5 1437.25  4927.1 1436.59  4950.9 1435.01
  4975.7 1434.44  4994.3 1435.40  5045.7 1433.20  5045.9 1432.70  5049.4 1432.70
  5049.7 1433.20  5059.3 1433.46  5081.9 1436.50  5101.5 1437.32  5138.4 1440.40
  5163.7 1443.15  5181.0 1444.20  5205.8 1449.27  5219.3 1450.22  5229.1 1452.41
  5245.5 1454.50  5261.8 1458.82  5288.5 1463.42  5314.2 1472.68  5317.5 1474.94
  5326.0 1476.50  5331.5 1476.62  5345.7 1478.71  5354.3 1479.69  5369.9 1480.21
#Mann=5,-1,0
  4846.8    0.07       0  5045.7    0.05       0  5049.7    0.07       0
  5138.4   0.035       0  5345.7    0.07       0
Bank Sta=5045.7,5049.7
Exp/Cntr=0.3,0.1

Type RM Length L Ch R = 1,833,484,484,484
BEGIN DESCRIPTION:
Stream0021 0.2
END DESCRIPTION:
XS GIS Cut Line= 4
      1998035.57     13892334.82      1998035.59     13892334.83
      1998220.27     13892533.03      1998359.89     13892704.18
#Sta/Elev= 30
  4908.8 1425.01  4947.2 1425.41  4985.4 1425.03  4996.8 1424.49  4997.3 1423.99
  5003.2 1423.99  5003.7 1424.49  5030.0 1424.99  5087.4 1427.29  5099.5 1427.36
  5105.0 1426.66  5141.7 1428.13  5180.9 1429.18  5200.3 1431.24  5209.1 1431.95
  5216.6 1433.70  5236.8 1436.46  5245.3 1438.23  5256.0 1438.95  5260.3 1440.20
  5263.1 1440.48  5270.9 1442.93  5311.4 1446.90  5334.9 1450.29  5342.2 1451.89
  5359.9 1454.68  5369.0 1456.79  5379.2 1460.15  5386.1 1461.22  5400.6 1465.13
#Mann=5,-1,0
  4908.8    0.07       0  4996.8    0.05       0  5003.7    0.07       0
  5141.7   0.035       0  5200.3    0.07       0
Bank Sta=4996.8,5003.7
Exp/Cntr=0.3,0.1

Type RM Length L Ch R = 1,349,0,0,0
BEGIN DESCRIPTION:
Stream0021 0.0
END DESCRIPTION:
XS GIS Cut Line= 3
      1997495.09     13892587.12      1997850.90     13892776.27
      1998008.58     13892902.42
#Sta/Elev= 30
  4545.0 1423.41  4557.0 1423.76  4668.6 1423.16  4677.9 1422.57  4689.7 1422.72
  4725.9 1421.54  4765.1 1421.31  4792.2 1421.23  4816.3 1421.99  4896.5 1422.02
  4915.9 1421.42  4955.4 1421.54  4975.7 1420.71  4976.2 1420.21  4982.3 1420.21
  4982.8 1420.71  5006.1 1421.29  5017.3 1421.87  5025.4 1422.82  5032.3 1425.01
  5036.9 1427.03  5053.6 1435.43  5064.3 1438.97  5067.6 1439.57  5074.9 1439.97
  5090.7 1439.41  5105.9 1440.01  5121.9 1442.25  5132.9 1442.78  5149.9 1444.95
#Mann=4,-1,0
  4545.0    0.07       0  4975.7   0.035       0  4982.8   0.035       0
  5105.9    0.07       0
Bank Sta=4975.7,4982.8
Exp/Cntr=0.3,0.1

Chan Stop Cuts=-1