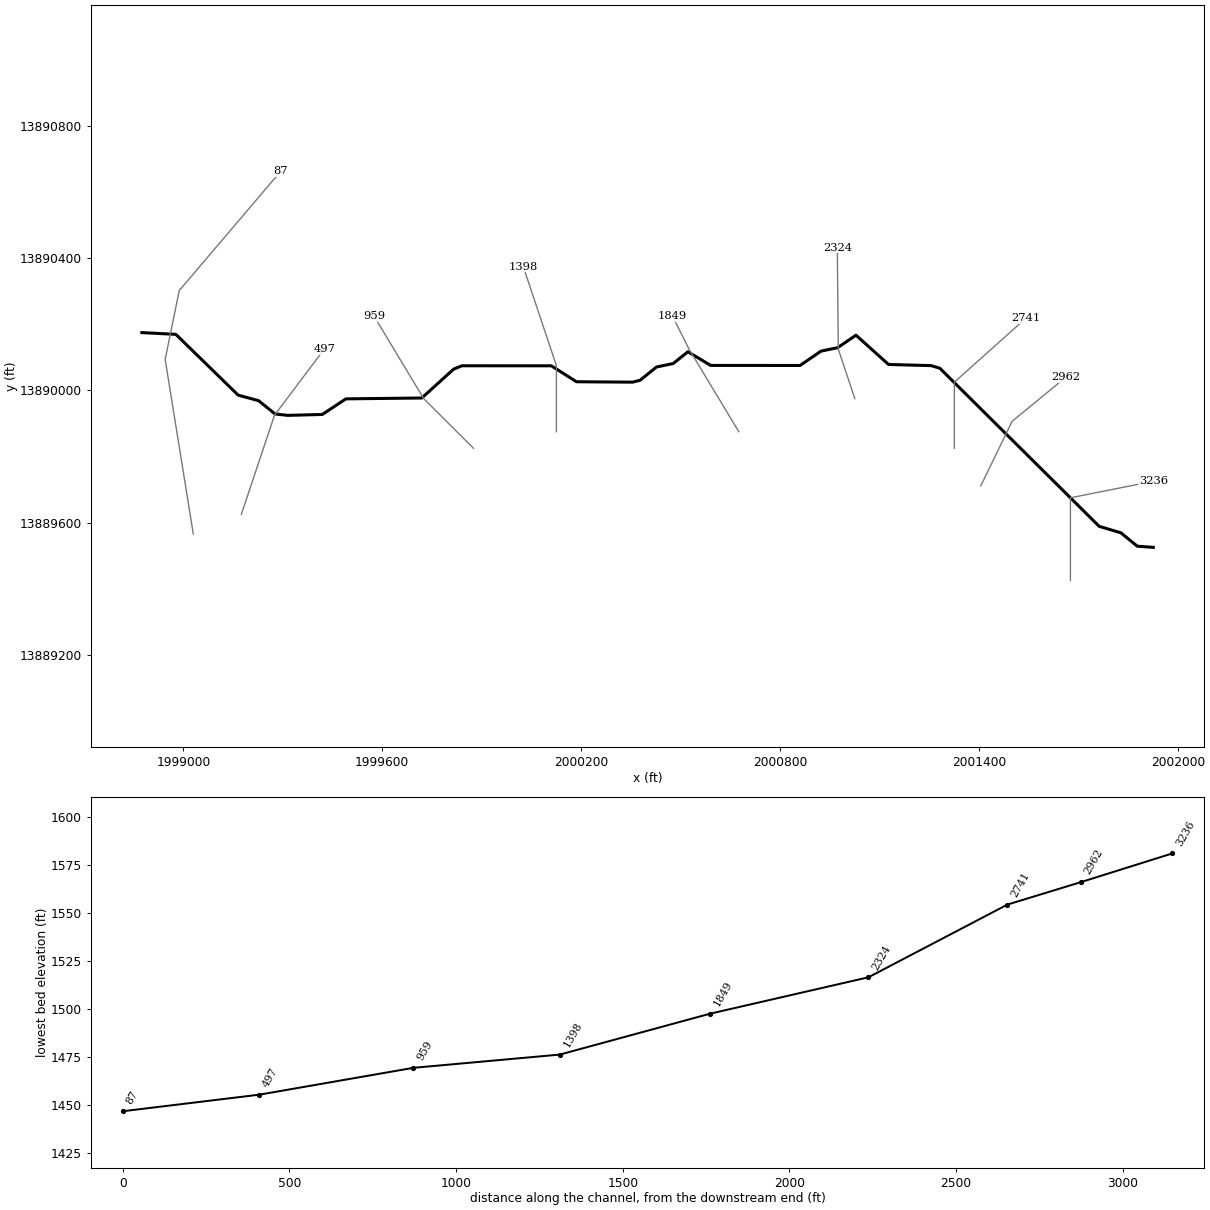
--- Stream0023.prj (project) ---

Proj Title=Stream0023 Base Level Engineering
Current Plan=p01
Default Exp/Contr=0.3,0.1
English Units
Geom File=g01
Flow File=f01
Plan File=p01
Y Axis Title=Elevation
X Axis Title(PF)=Main Channel Distance
X Axis Title(XS)=Station
BEGIN DESCRIPTION:
Stream0023
END DESCRIPTION:
DSS Export Rating Curves= 0
DSS Export Rating Curve Sorted= 0
DSS Export Volume Flow Curves= 0
DXF OffsetX= 0
DXF OffsetY= 0
DXF ScaleX= 1
DXF ScaleY= 10

--- Stream0023.p01 (plan) ---

Plan Title=Multiple Run
Short Identifier=Multiple
Geom File=g01
Flow File=f01
Subcritical Flow
K Sum by GR= 0
Std Step Tol= 0.01
Critical Tol= 0.01
Num of Std Step Trials= 20
Max Error Tol= 0.3
Flow Tol Ratio= 0.001
Split Flow NTrial= 30
Split Flow Tol= 0.02
Split Flow Ratio= 0.02
Log Output Level= 0
Friction Slope Method= 1
Unsteady Friction Slope Method= 2
Unsteady Bridges Friction Slope Method= 1
Parabolic Critical Depth
Global Vel Dist=  1 , 1 , 1
Global Log Level= 0
CheckData=True
Encroach Param= -1, 0, 0, 0
BEGIN DESCRIPTION:
Multiple Run
END DESCRIPTION:

--- Stream0023.f01 (steady flow) ---

Flow Title=Multiple
Program Version=4.10
Number of Profiles= 7
Profile Names=10-year,25-year,50-year,1pct_min,100-year,1pct_plu,500-year
River Rch & RM=Stream0023,Reach-1         ,3236
     233     361     474     304     607    1211     978
River Rch & RM=Stream0023,Reach-1         ,2741
     603    1003    1378     923    1841    3673    3239
Boundary for River Rch & Prof#=Stream0023,Reach-1         , 1
Up Type= 0
Dn Type= 3
Dn Slope=0.008
Boundary for River Rch & Prof#=Stream0023,Reach-1         , 2
Up Type= 0
Dn Type= 3
Dn Slope=0.008
Boundary for River Rch & Prof#=Stream0023,Reach-1         , 3
Up Type= 0
Dn Type= 3
Dn Slope=0.008
Boundary for River Rch & Prof#=Stream0023,Reach-1         , 4
Up Type= 0
Dn Type= 3
Dn Slope=0.008
Boundary for River Rch & Prof#=Stream0023,Reach-1         , 5
Up Type= 0
Dn Type= 3
Dn Slope=0.008
Boundary for River Rch & Prof#=Stream0023,Reach-1         , 6
Up Type= 0
Dn Type= 3
Dn Slope=0.008
Boundary for River Rch & Prof#=Stream0023,Reach-1         , 7
Up Type= 0
Dn Type= 3
Dn Slope=0.008
DSS Import GetInterval= 0
DSS Import GetPeak= 0
DSS Import FillOption= 0

--- Stream0023.g01 (geometry) ---

Geom Title=Existing Conditions
Program Version=4.10

River Reach=Stream0023      ,Reach-1
Reach XY= 30
        2001925.       13889525.      2001876.49      13889528.6
      2001827.24     13889569.03      2001761.78     13889588.61
      2001281.19     13890067.18      2001255.01     13890075.02
      2001126.47     13890078.57       2001028.4     13890167.22
      2000973.37     13890129.43      2000922.83     13890118.91
      2000859.79     13890075.51      2000590.16     13890075.66
      2000521.68     13890116.96      2000477.29     13890081.39
      2000426.75     13890070.84      2000377.35     13890030.71
      2000354.97     13890025.06      2000185.51     13890026.22
      2000109.78     13890074.48      1999840.16     13890074.61
      1999815.21      13890064.5      1999719.14     13889977.07
      1999490.22     13889974.48      1999419.06     13889927.25
      1999314.83      13889924.5      1999276.56     13889928.74
      1999227.17     13889968.86      1999165.32     13889985.76
       1998977.5     13890169.65        1998875.       13890175.

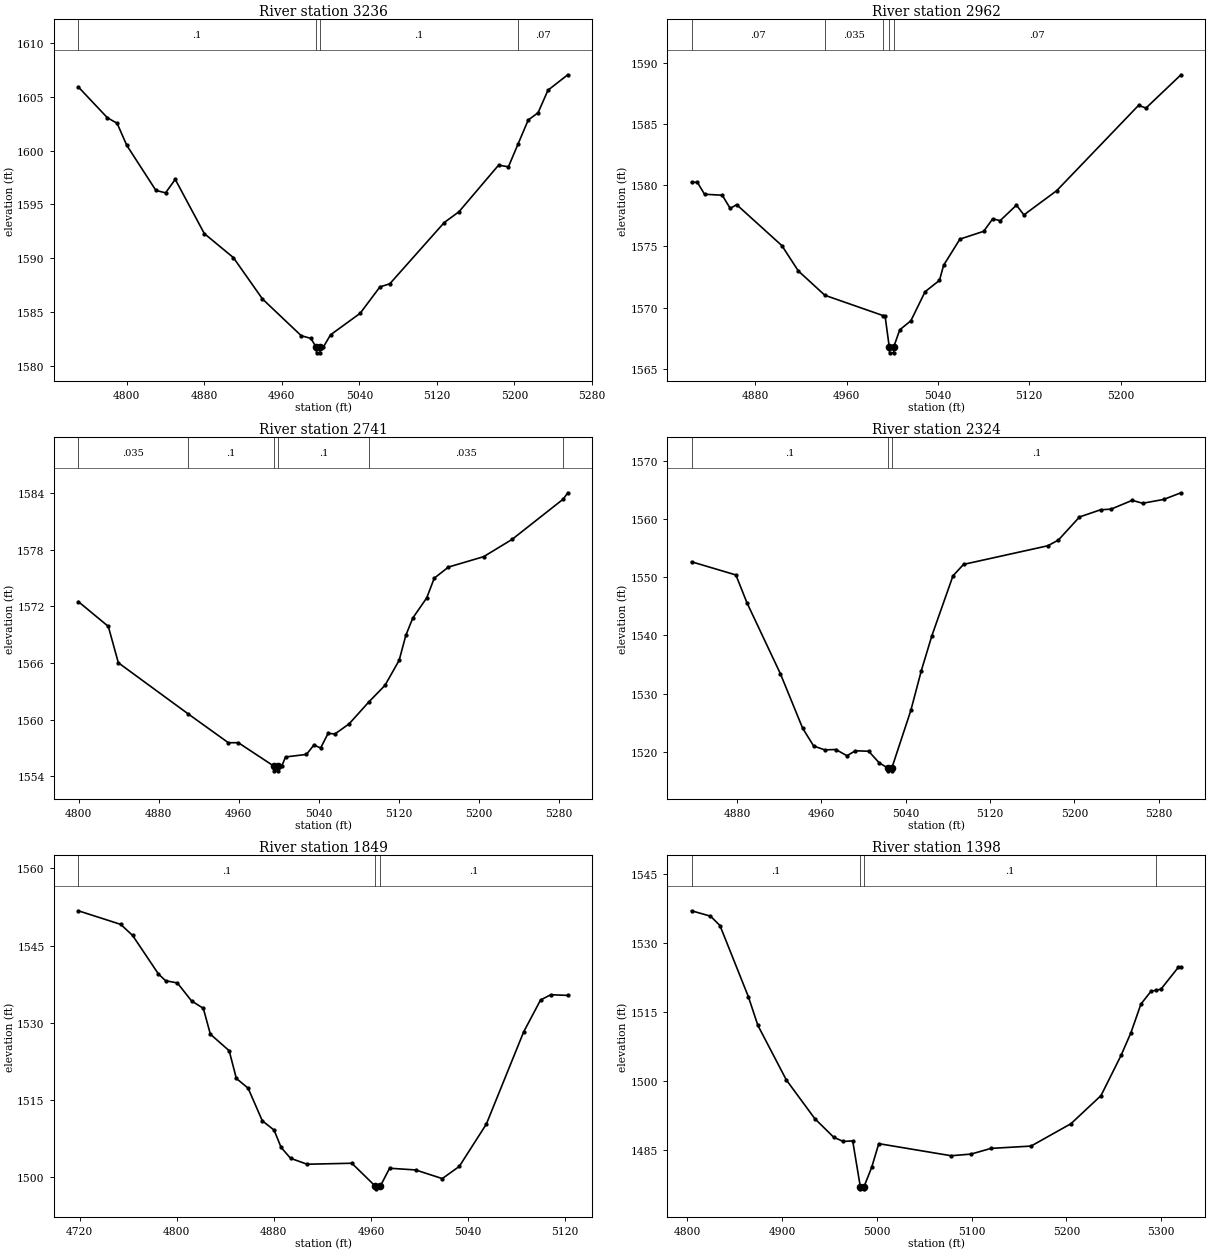
Type RM Length L Ch R = 1 ,3236    ,274,274,274
BEGIN DESCRIPTION:
Stream0023 7.0
END DESCRIPTION:
XS GIS Cut Line= 3
        2001675.     13889424.98        2001675.       13889675.
      2001925.03     13889725.01
#Sta/Elev= 30
    4750  1605.9    4780 1603.04    4790 1602.53    4800 1600.48    4830  1596.3
    4840 1596.07    4850 1597.32    4880 1592.29    4910 1590.06    4940 1586.22
    4980 1582.81    4990 1582.56  4995.5 1581.72  4995.8 1581.22  4999.3 1581.22
  4999.5 1581.72  5002.6 1581.72  5010.2 1582.89  5040.8 1584.89  5061.2 1587.34
  5071.4 1587.63  5127.5 1593.31  5142.8 1594.32  5183.6 1598.64  5193.8 1598.49
  5203.7  1600.6  5214.2 1602.83  5224.4 1603.51  5234.6  1605.6    5255 1607.03
#Mann= 4 ,-1 , 0
    4750      .1       0  4995.5     .05       0  4999.5      .1       0
  5203.7     .07       0
Bank Sta=4995.5,4999.5
XS Rating Curve= 0 ,0
Exp/Cntr=0.3,0.1

Type RM Length L Ch R = 1 ,2962    ,221,221,221
BEGIN DESCRIPTION:
Mapping XS f66109d8
END DESCRIPTION:
XS GIS Cut Line= 3
      2001404.56     13889710.82      2001499.02     13889906.33
      2001662.17      13890040.7
#Sta/Elev= 30
  4824.3 1580.25  4829.4 1580.25  4835.7 1579.27  4851.2 1579.19  4858.2 1578.11
  4863.8 1578.42  4903.4 1575.07  4917.8    1573    4941 1571.01  4992.2 1569.34
  4993.8 1569.29  4997.4  1566.8  4997.7  1566.3  5001.2  1566.3  5001.4  1566.8
  5006.6 1568.18  5016.4 1568.93  5028.8  1571.3  5041.4 1572.23    5045 1573.46
  5059.3  1575.6  5080.1 1576.24    5088 1577.26  5094.5 1577.11  5108.8 1578.38
  5115.3 1577.58    5144 1579.56  5215.7 1586.54  5222.2 1586.32  5252.8 1589.04
#Mann= 5 ,-1 , 0
  4824.3     .07       0    4941    .035       0  4992.2     .07       0
  4997.4     .05       0  5001.4     .07       0
Bank Sta=4997.4,5001.4
XS Rating Curve= 0 ,0
Exp/Cntr=0.3,0.1

Type RM Length L Ch R = 1 ,2741    ,417,417,417
BEGIN DESCRIPTION:
Stream0023 6.0
END DESCRIPTION:
XS GIS Cut Line= 3
        2001325.     13889824.95        2001325.       13890025.
      2001540.43     13890218.17
#Sta/Elev= 30
  4799.7 1572.51  4829.7 1569.88  4839.7 1566.03  4909.2 1560.64  4949.7 1557.56
  4959.7 1557.56  4995.2 1555.08  4995.5 1554.58    4999 1554.58  4999.2 1555.08
  5003.1 1555.08  5006.9 1556.05  5027.8 1556.32  5035.3 1557.32    5042    1557
  5049.5 1558.56  5056.2 1558.48  5070.4 1559.55  5090.3 1561.89  5106.3 1563.63
  5120.5 1566.29  5127.2 1568.94  5134.1 1570.76  5148.1 1572.91  5155.6 1574.99
  5169.8 1576.17    5205 1577.27  5233.4  1579.1  5284.6 1583.37  5289.1 1584.04
#Mann= 6 ,-1 , 0
  4799.7    .035       0  4909.2      .1       0  4995.2     .05       0
  4999.2      .1       0  5090.3    .035       0  5284.6     .07       0
Bank Sta=4995.2,4999.2
XS Rating Curve= 0 ,0
Exp/Cntr=0.3,0.1

Type RM Length L Ch R = 1 ,2324    ,475,475,475
BEGIN DESCRIPTION:
Stream0023 5.0
END DESCRIPTION:
XS GIS Cut Line= 3
      2001024.99     13889975.04        2000975.       13890125.
      2000972.13     13890431.31
#Sta/Elev= 30
  4836.7 1552.63  4878.8 1550.37  4889.4 1545.55    4921 1533.42  4942.1 1524.07
  4952.6 1520.99  4963.1 1520.33  4973.7 1520.39  4984.2 1519.32  4992.1 1520.17
  5004.8  1520.1  5014.8  1518.1  5022.8 1517.23    5023 1516.73  5026.5 1516.73
  5026.8 1517.23  5044.8  1527.1  5054.8 1533.96  5064.8 1539.95  5084.8 1550.22
  5094.8 1552.18  5174.8 1555.38  5184.8 1556.36  5204.8 1560.32  5224.8 1561.56
  5234.8 1561.67  5254.8 1563.18  5264.8 1562.68  5284.8 1563.34  5301.1 1564.48
#Mann= 3 ,-1 , 0
  4836.7      .1       0  5022.8     .05       0  5026.8      .1       0
Bank Sta=5022.8,5026.8
XS Rating Curve= 0 ,0
Exp/Cntr=0.3,0.1

Type RM Length L Ch R = 1 ,1849    ,451,451,451
BEGIN DESCRIPTION:
Stream0023 4.0
END DESCRIPTION:
XS GIS Cut Line= 3
      2000674.98     13889875.04        2000525.       13890125.
        2000475.     13890224.99
#Sta/Elev= 30
  4718.9 1551.77  4753.8 1549.13  4763.6 1546.99  4784.9  1539.5  4790.8 1538.19
  4800.5 1537.76  4812.2 1534.27  4821.9 1532.83  4827.7 1527.81  4843.2  1524.6
  4849.1 1519.22  4858.8 1517.33  4870.5 1510.99  4880.2 1509.19    4886 1505.82
  4893.8 1503.71  4907.4 1502.56  4944.3 1502.75  4963.7 1498.28  4963.9 1497.78
  4967.7 1498.28  4975.4 1501.78  4996.8 1501.45  5018.8 1499.77  5032.8 1502.13
  5055.1 1510.34  5085.9 1528.27  5099.8 1534.45  5108.2 1535.47  5122.2 1535.34
#Mann= 3 ,-1 , 0
  4718.9      .1       0  4963.7     .05       0  4967.7      .1       0
Bank Sta=4963.7,4967.7
XS Rating Curve= 0 ,0
Exp/Cntr=0.3,0.1

Type RM Length L Ch R = 1 ,1398    ,439,439,439
BEGIN DESCRIPTION:
Stream0023 3.0
END DESCRIPTION:
XS GIS Cut Line= 3
        2000125.     13889875.03        2000125.       13890075.
        2000025.       13890375.
#Sta/Elev= 30
  4804.6 1536.98  4824.6 1535.81  4834.6 1533.77  4864.6 1518.27  4874.6 1512.04
  4904.6 1500.18  4934.6 1491.77  4954.6 1487.71  4964.6  1486.8  4974.6 1486.92
  4982.6 1476.99  4982.8 1476.49  4986.3 1476.49  4986.6 1476.99  4994.6 1481.15
  5002.1 1486.32  5078.4 1483.69  5099.4 1484.05  5120.5 1485.29  5162.7 1485.79
  5204.8 1490.66  5236.5 1496.78  5257.6  1505.5  5268.1 1510.48  5278.6 1516.69
  5289.2 1519.46  5294.1 1519.67  5299.7 1519.92  5318.2 1524.73  5320.8 1524.73
#Mann= 4 ,-1 , 0
  4804.6      .1       0  4982.6     .05       0  4986.6      .1       0
  5294.1     .07       0
Bank Sta=4982.6,4986.6
XS Rating Curve= 0 ,0
Exp/Cntr=0.3,0.1

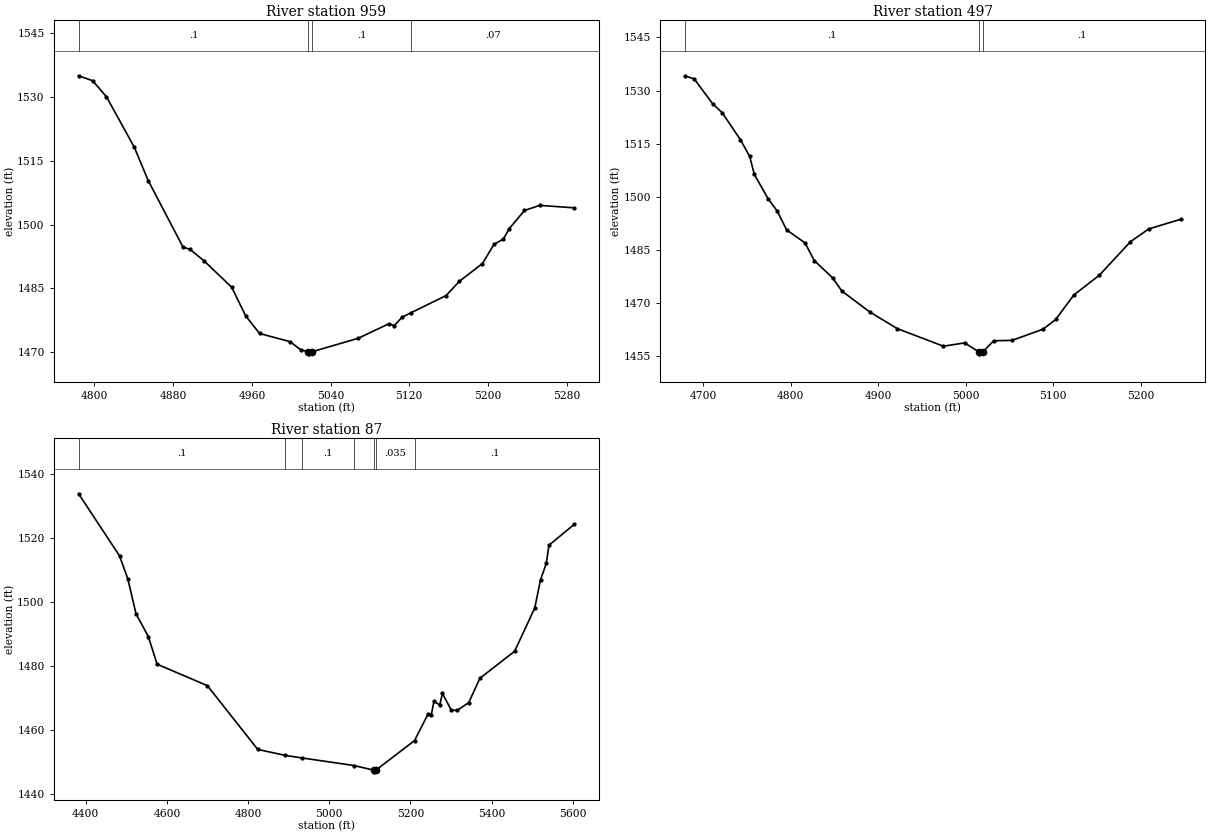
Type RM Length L Ch R = 1 ,959     ,462,462,462
BEGIN DESCRIPTION:
Stream0023 2.0
END DESCRIPTION:
XS GIS Cut Line= 3
      1999875.03     13889824.97        1999725.       13889975.
      1999575.01     13890224.98
#Sta/Elev= 30
  4783.9 1534.98  4798.1 1533.82  4812.2 1530.05  4840.5 1518.16  4854.7 1510.31
    4890  1494.7  4897.1 1494.16  4911.2 1491.51  4939.5 1485.25  4953.7 1478.53
  4967.8 1474.39    4999 1472.45  5009.7 1470.53  5017.4  1470.1  5017.7  1469.6
  5021.4  1470.1    5068 1473.25  5099.1 1476.65  5104.9 1476.26  5112.7 1478.22
  5122.1  1479.3  5157.4  1483.3    5171 1486.67  5194.3 1490.82    5206 1495.31
  5215.7 1496.61  5221.5 1499.01  5237.1 1503.31  5252.6 1504.51  5287.6 1503.93
#Mann= 4 ,-1 , 0
  4783.9      .1       0  5017.4     .05       0  5021.4      .1       0
  5122.1     .07       0
Bank Sta=5017.4,5021.4
XS Rating Curve= 0 ,0
Exp/Cntr=0.3,0.1

Type RM Length L Ch R = 1 ,497     ,410,410,410
BEGIN DESCRIPTION:
Stream0023 1.0
END DESCRIPTION:
XS GIS Cut Line= 3
      1999174.99     13889624.98        1999275.       13889925.
      1999425.03     13890125.04
#Sta/Elev= 30
  4679.5 1534.17  4690.1 1533.24  4711.1 1526.23  4721.7 1523.79  4742.8 1516.09
  4753.3 1511.39  4758.6 1506.32  4774.4 1499.42  4784.9 1495.92  4795.5 1490.64
  4816.6 1486.95  4827.1 1481.98  4848.2 1477.07  4858.7 1473.36  4890.3  1467.5
    4922 1462.75  4974.7 1457.79  4998.9 1458.72  5015.6 1456.13  5015.9 1455.63
  5019.6 1456.13  5032.2 1459.32    5053 1459.43  5088.5 1462.57    5103 1465.34
  5123.9 1472.29    5153 1477.85  5188.5 1487.32  5209.3  1490.9  5245.8 1493.64
#Mann= 3 ,-1 , 0
  4679.5      .1       0  5015.6     .05       0  5019.6      .1       0
Bank Sta=5015.6,5019.6
XS Rating Curve= 0 ,0
Exp/Cntr=0.3,0.1

Type RM Length L Ch R = 1 ,87      ,0,0,0
BEGIN DESCRIPTION:
Stream0023 0.0
END DESCRIPTION:
XS GIS Cut Line= 4
      1999030.09     13889565.44      1998945.28      13890093.8
      1998987.65     13890302.04      1999293.67     13890663.19
#Sta/Elev= 30
  4382.4 1533.96  4483.2 1514.54  4503.5 1507.41  4523.7 1496.46  4554.1 1489.32
  4575.8 1480.66  4699.7 1473.95  4823.6 1454.02  4891.2 1452.15  4933.2 1451.34
  5060.6 1448.98  5110.6  1447.5  5110.9    1447  5114.6  1447.5    5210 1456.77
  5243.6 1465.13  5251.4 1464.85  5257.9 1469.08  5272.2 1467.91  5278.8 1471.51
  5300.8 1466.25  5315.1 1466.22  5343.6 1468.64    5371 1476.25  5456.8 1484.72
  5506.2 1498.22  5520.5 1507.05  5534.8 1512.23  5541.3 1517.88  5603.4 1524.38
#Mann= 7 ,-1 , 0
  4382.4      .1       0  4891.2    .035       0  4933.2      .1       0
  5060.6    .035       0  5110.6     .05       0  5114.6    .035       0
    5210      .1       0
Bank Sta=5110.6,5114.6
XS Rating Curve= 0 ,0
Exp/Cntr=0.3,0.1

Chan Stop Cuts=-1
Use User Specified Reach Order=0
Composite Channel Slope=5