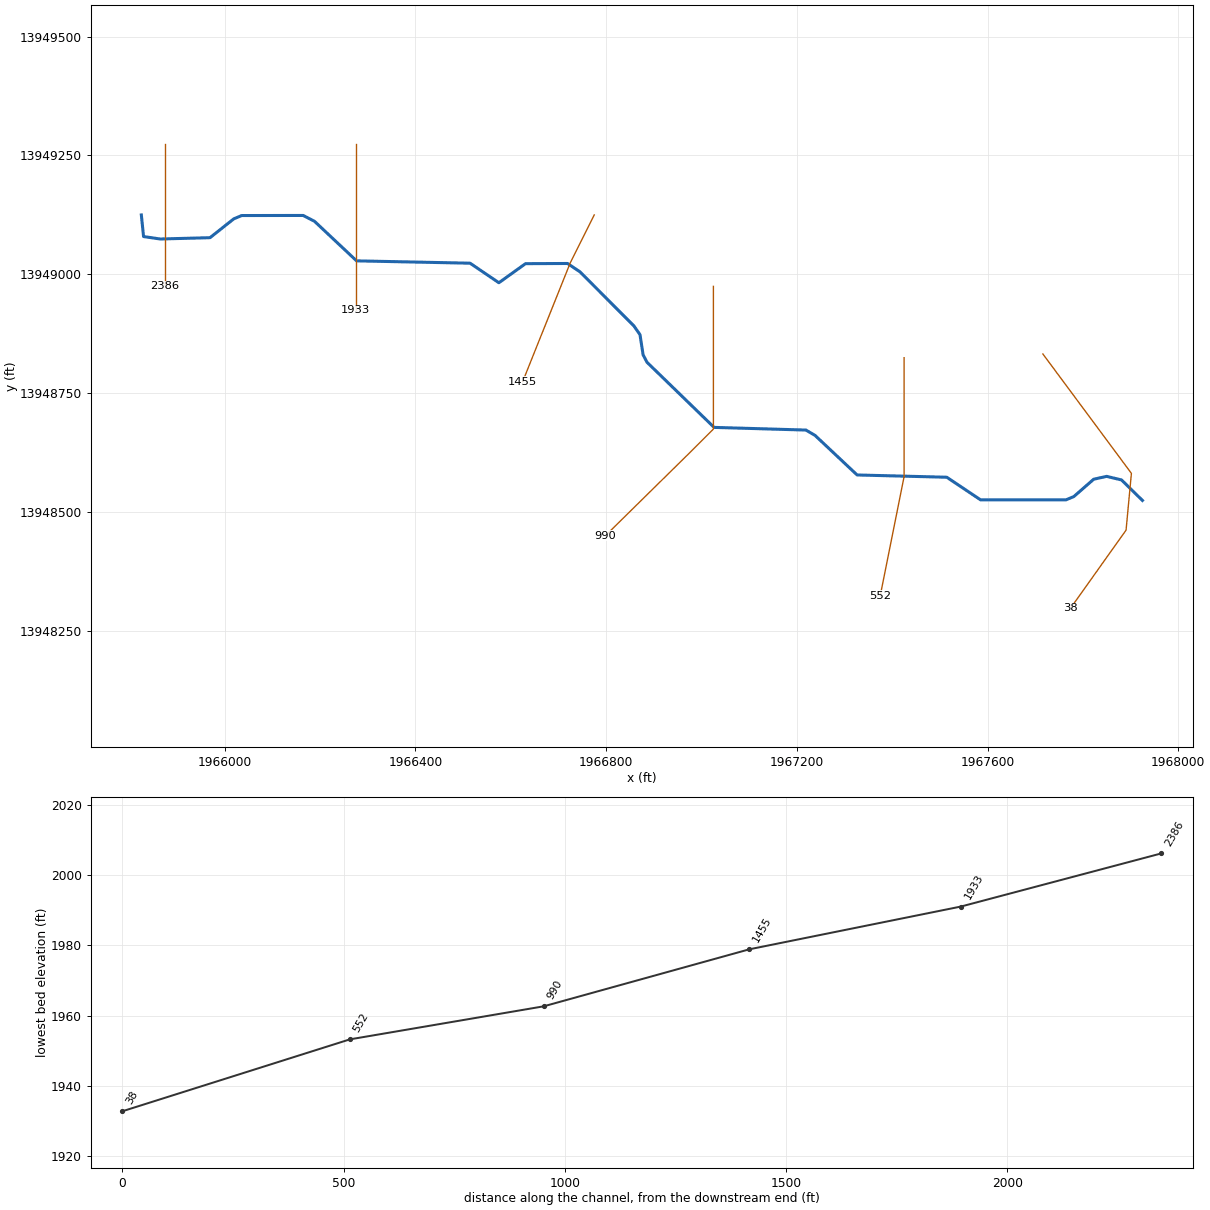
--- Stream0024.prj (project) ---

Proj Title=Stream0024 Base Level Engineering
Current Plan=p01
Default Exp/Contr=0.3,0.1
English Units
Geom File=g01
Flow File=f01
Plan File=p01
BEGIN DESCRIPTION:
Stream0024
END DESCRIPTION:

--- Stream0024.p01 (plan) ---

Plan Title=Multiple Run
Short Identifier=Multiple
Geom File=g01
Flow File=f01
Subcritical Flow
K Sum by GR= 0
Std Step Tol= 0.01
Critical Tol= 0.01
Num of Std Step Trials= 20
Max Error Tol= 0.3
Flow Tol Ratio= 0.001
Split Flow NTrial= 30
Split Flow Tol= 0.02
Split Flow Ratio= 0.02
Log Output Level= 0
Friction Slope Method= 1
Unsteady Friction Slope Method= 2
Unsteady Bridges Friction Slope Method= 1
Parabolic Critical Depth
Global Vel Dist=  1 , 1 , 1
Global Log Level= 0
CheckData=True
Encroach Param= -1, 0, 0, 0
BEGIN DESCRIPTION:
Multiple Run
END DESCRIPTION:

--- Stream0024.f01 (steady flow) ---

Flow Title=Multiple
Number of Profiles=7
Profile Names=10-year,25-year,50-year,1pct_min,100-year,1pct_plu,500-year
River Rch & RM= Stream0024,Reach-1,2386
     280     435     570     364     726    1449    1158
River Rch & RM= Stream0024,Reach-1,1455
     394     627     837     542    1082    2159    1780
Boundary for River Rch & Prof#=Stream0024,Reach-1,1
Up Type=0
Dn Type=3
Dn Slope=0.005
Boundary for River Rch & Prof#=Stream0024,Reach-1,2
Up Type=0
Dn Type=3
Dn Slope=0.005
Boundary for River Rch & Prof#=Stream0024,Reach-1,3
Up Type=0
Dn Type=3
Dn Slope=0.005
Boundary for River Rch & Prof#=Stream0024,Reach-1,4
Up Type=0
Dn Type=3
Dn Slope=0.005
Boundary for River Rch & Prof#=Stream0024,Reach-1,5
Up Type=0
Dn Type=3
Dn Slope=0.005
Boundary for River Rch & Prof#=Stream0024,Reach-1,6
Up Type=0
Dn Type=3
Dn Slope=0.005
Boundary for River Rch & Prof#=Stream0024,Reach-1,7
Up Type=0
Dn Type=3
Dn Slope=0.005

--- Stream0024.g01 (geometry) ---

Geom Title=Existing Conditions

River Reach=Stream0024,Reach-1
Reach XY= 30
      1965825.00     13949125.00      1965829.63     13949079.62
      1965864.57     13949074.49      1965969.06     13949077.24
      1966018.95     13949116.86      1966035.51     13949123.79
      1966164.56     13949123.96      1966188.30     13949111.60
      1966276.47     13949028.55      1966514.56     13949023.62
      1966575.00     13948982.56      1966630.90     13949022.64
      1966719.11     13949023.03      1966745.16     13949005.42
      1966858.35     13948891.67      1966871.02     13948873.35
      1966877.53     13948831.05      1966885.78     13948815.32
      1967026.46     13948678.54      1967219.14     13948672.93
      1967238.31     13948661.60      1967326.47     13948578.55
      1967514.49     13948573.78      1967585.51     13948526.22
      1967764.51     13948526.23      1967781.08     13948533.16
      1967822.78     13948569.63      1967849.95     13948575.61
      1967881.15     13948568.05      1967925.00     13948525.00

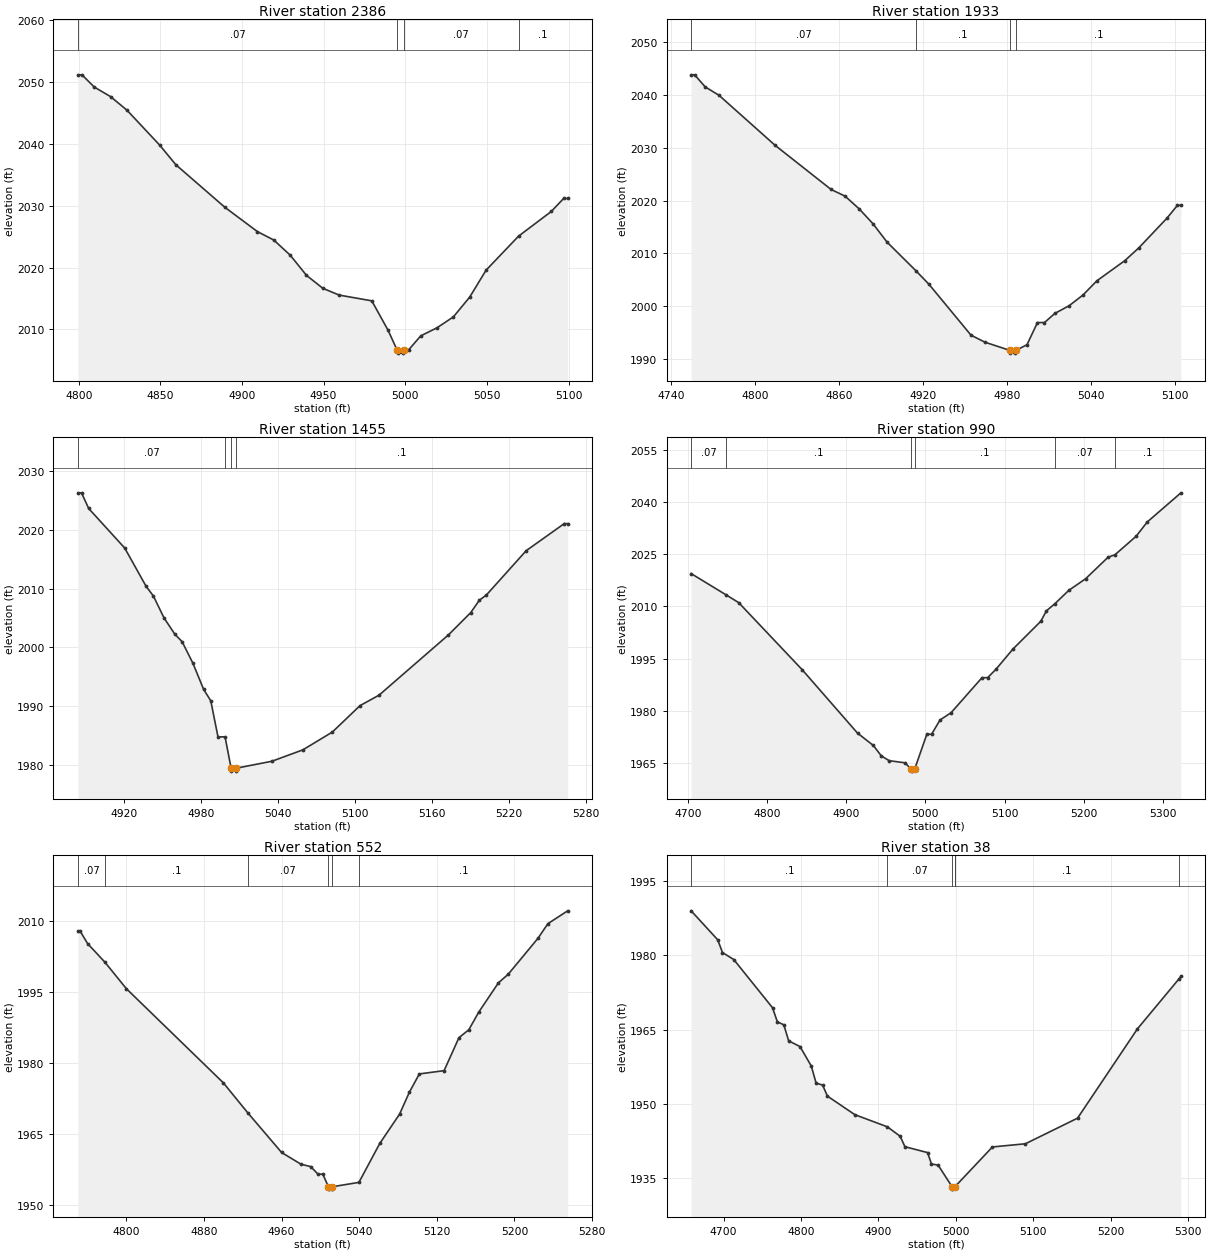
Type RM Length L Ch R = 1,2386,453,453,453
BEGIN DESCRIPTION:
Stream0024 5.0
END DESCRIPTION:
XS GIS Cut Line= 3
      1965875.00     13949275.02      1965875.00     13949075.00
      1965875.00     13948975.02
#Sta/Elev= 30
  4799.5 2051.15  4802.0 2051.15  4809.5 2049.18  4819.5 2047.63  4829.5 2045.45
  4849.5 2039.82  4859.5 2036.62  4889.5 2029.75  4909.5 2025.81  4919.5 2024.45
  4929.5 2022.02  4939.5 2018.75  4949.5 2016.66  4959.5 2015.56  4979.5 2014.63
  4989.5 2009.87  4995.0 2006.68  4995.3 2006.18  4998.8 2006.18  4999.0 2006.68
  5002.0 2006.68  5009.5 2008.97  5019.5 2010.28  5029.5 2012.04  5039.5 2015.24
  5049.5 2019.58  5069.4 2025.08  5089.5 2029.08  5097.0 2031.17  5099.5 2031.17
#Mann=4,-1,0
  4799.5    0.07       0  4995.0    0.05       0  4999.0    0.07       0
  5069.4     0.1       0
Bank Sta=4995,4999
Exp/Cntr=0.3,0.1

Type RM Length L Ch R = 1,1933,478,478,478
BEGIN DESCRIPTION:
Stream0024 4.0
END DESCRIPTION:
XS GIS Cut Line= 3
      1966275.00     13949274.97      1966275.00     13949025.00
      1966275.00     13948924.97
#Sta/Elev= 30
  4754.3 2043.84  4756.8 2043.84  4764.3 2041.56  4774.3 2039.94  4814.3 2030.47
  4854.3 2022.10  4864.3 2020.83  4874.3 2018.44  4884.3 2015.58  4894.3 2012.11
  4914.9 2006.69  4924.3 2004.10  4954.3 1994.46  4964.3 1993.13  4982.3 1991.56
  4982.5 1991.06  4986.0 1991.06  4986.3 1991.56  4994.3 1992.66  5001.8 1996.86
  5006.8 1996.86  5014.3 1998.61  5024.3 2000.03  5034.3 2002.08  5044.3 2004.79
  5064.3 2008.62  5074.3 2011.05  5094.3 2016.65  5101.8 2019.09  5104.3 2019.09
#Mann=4,-1,0
  4754.3    0.07       0  4914.9     0.1       0  4982.3    0.05       0
  4986.3     0.1       0
Bank Sta=4982.3,4986.3
Exp/Cntr=0.3,0.1

Type RM Length L Ch R = 1,1455,465,465,465
BEGIN DESCRIPTION:
Stream0024 3.0
END DESCRIPTION:
XS GIS Cut Line= 3
      1966775.01     13949125.02      1966725.00     13949025.00
      1966624.99     13948774.98
#Sta/Elev= 30
  4884.4 2026.32  4887.2 2026.32  4892.8 2023.65  4920.8 2016.92  4937.5 2010.38
  4943.1 2008.75  4951.5 2004.97  4959.9 2002.21  4965.5 2000.95  4973.9 1997.28
  4982.2 1992.84  4987.8 1990.88  4993.4 1984.74  4998.9 1984.74  5003.6 1979.40
  5003.9 1978.90  5007.4 1978.90  5007.6 1979.40  5035.3 1980.58  5059.5 1982.53
  5082.4 1985.56  5103.9 1990.06  5118.7 1991.84  5172.6 2002.09  5190.1 2005.92
  5196.8 2008.03  5202.2 2008.90  5233.2 2016.46  5262.8 2021.07  5265.5 2021.07
#Mann=4,-1,0
  4884.4    0.07       0  4998.9     0.1       0  5003.6    0.05       0
  5007.6     0.1       0
Bank Sta=5003.6,5007.6
Exp/Cntr=0.3,0.1

Type RM Length L Ch R = 1,990,438,438,438
BEGIN DESCRIPTION:
Stream0024 2.0
END DESCRIPTION:
XS GIS Cut Line= 4
      1967025.00     13948974.96      1967025.00     13948675.00
      1966975.00     13948625.00      1966798.75     13948451.19
#Sta/Elev= 30
  4704.3 2019.45  4748.7 2013.30  4764.3 2011.11  4844.3 1991.86  4914.3 1973.60
  4934.3 1970.04  4944.3 1967.06  4954.3 1965.67  4974.3 1965.06  4982.3 1963.17
  4982.5 1962.67  4986.3 1963.17  5001.8 1973.28  5007.8 1973.28  5018.4 1977.36
  5032.5 1979.49  5071.4 1989.53  5078.5 1989.53  5089.1 1991.96  5110.3 1997.72
  5145.6 2005.74  5152.8 2008.76  5163.6 2010.84  5181.0 2014.64  5202.2 2017.97
  5230.5 2024.15  5239.1 2024.84  5265.9 2030.17  5280.0 2034.29  5322.5 2042.67
#Mann=6,-1,0
  4704.3    0.07       0  4748.7     0.1       0  4982.3    0.05       0
  4986.3     0.1       0  5163.6    0.07       0  5239.1     0.1       0
Bank Sta=4982.3,4986.3
Exp/Cntr=0.3,0.1

Type RM Length L Ch R = 1,552,514,514,514
BEGIN DESCRIPTION:
Stream0024 1.0
END DESCRIPTION:
XS GIS Cut Line= 3
      1967425.00     13948824.98      1967425.00     13948575.00
      1967375.01     13948325.04
#Sta/Elev= 30
  4750.0 2007.84  4752.5 2007.84  4760.0 2005.27  4777.9 2001.32  4800.0 1995.71
  4900.0 1975.77  4925.2 1969.41  4960.0 1961.03  4980.0 1958.54  4990.0 1958.04
  4997.5 1956.44  5002.5 1956.44  5008.2 1953.77  5008.4 1953.27  5011.9 1953.27
  5012.2 1953.77  5039.7 1954.70  5061.2 1962.95  5081.6 1969.15  5091.8 1973.84
  5102.0 1977.67  5127.5 1978.36  5142.8 1985.34  5153.0 1987.03  5163.2 1990.75
  5183.5 1996.96  5193.7 1998.80  5224.3 2006.40  5234.5 2009.49  5254.9 2012.21
#Mann=6,-1,0
  4750.0    0.07       0  4777.9     0.1       0  4925.2    0.07       0
  5008.2    0.05       0  5012.2    0.07       0  5039.7     0.1       0
Bank Sta=5008.2,5012.2
Exp/Cntr=0.3,0.1

Type RM Length L Ch R = 1,38,0,0,0
BEGIN DESCRIPTION:
Stream0024 0.0
END DESCRIPTION:
XS GIS Cut Line= 4
      1967716.14     13948832.84      1967901.85     13948581.93
      1967890.62     13948462.58      1967774.30     13948298.69
#Sta/Elev= 30
  4658.0 1988.97  4692.3 1983.13  4698.5 1980.56  4713.1 1979.14  4763.2 1969.41
  4769.4 1966.58  4777.8 1965.97  4784.0 1962.74  4798.7 1961.58  4813.3 1957.65
  4819.5 1954.20  4827.9 1953.82  4834.1 1951.59  4869.6 1947.84  4911.6 1945.39
  4928.1 1943.49  4934.3 1941.38  4963.6 1940.19  4968.6 1937.88  4977.1 1937.68
  4995.2 1933.32  4995.5 1932.82  4999.2 1933.32  4999.5 1933.40  5047.4 1941.33
  5090.0 1941.97  5157.4 1947.14  5234.8 1965.16  5288.5 1975.24  5291.0 1975.78
#Mann=6,-1,0
  4658.0     0.1       0  4911.6    0.07       0  4995.2    0.05       0
  4999.2    0.07       0  4999.5     0.1       0  5288.5    0.07       0
Bank Sta=4995.2,4999.2
Exp/Cntr=0.3,0.1

Chan Stop Cuts=-1