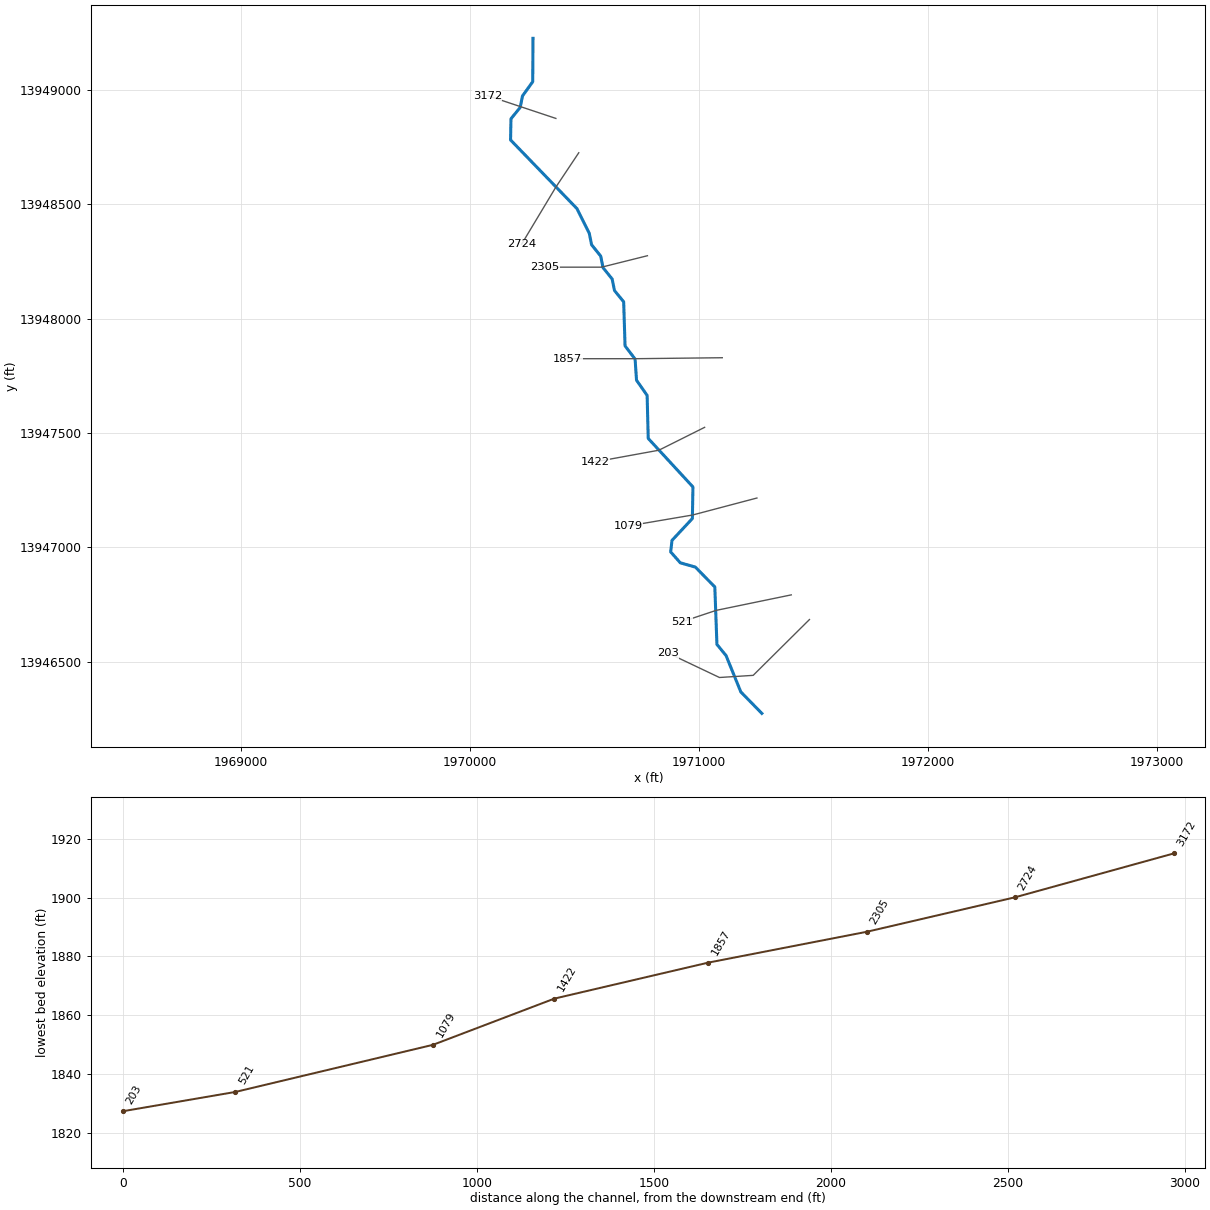
--- Stream0025.prj (project) ---

Proj Title=Stream0025 Base Level Engineering
Current Plan=p01
Default Exp/Contr=0.3,0.1
English Units
Geom File=g01
Flow File=f01
Plan File=p01
Y Axis Title=Elevation
X Axis Title(PF)=Main Channel Distance
X Axis Title(XS)=Station
BEGIN DESCRIPTION:
Stream0025
END DESCRIPTION:
DSS Export Rating Curves= 0
DSS Export Rating Curve Sorted= 0
DSS Export Volume Flow Curves= 0
DXF OffsetX= 0
DXF OffsetY= 0
DXF ScaleX= 1
DXF ScaleY= 10

--- Stream0025.p01 (plan) ---

Plan Title=Multiple Run
Short Identifier=Multiple
Geom File=g01
Flow File=f01
Subcritical Flow
K Sum by GR= 0
Std Step Tol= 0.01
Critical Tol= 0.01
Num of Std Step Trials= 20
Max Error Tol= 0.3
Flow Tol Ratio= 0.001
Split Flow NTrial= 30
Split Flow Tol= 0.02
Split Flow Ratio= 0.02
Log Output Level= 0
Friction Slope Method= 1
Unsteady Friction Slope Method= 2
Unsteady Bridges Friction Slope Method= 1
Parabolic Critical Depth
Global Vel Dist=  1 , 1 , 1
Global Log Level= 0
CheckData=True
Encroach Param= -1, 0, 0, 0
BEGIN DESCRIPTION:
Multiple Run
END DESCRIPTION:

--- Stream0025.f01 (steady flow) ---

Flow Title=Multiple
Number of Profiles=7
Profile Names=10-year,25-year,50-year,1pct_min,100-year,1pct_plu,500-year
River Rch & RM= Stream0025,Reach-1,3172
     259     409     542     351     701    1398    1157
River Rch & RM= Stream0025,Reach-1,2724
     409     667     905     597    1192    2379    2049
Boundary for River Rch & Prof#=Stream0025,Reach-1,1
Up Type=0
Dn Type=3
Dn Slope=0.005
Boundary for River Rch & Prof#=Stream0025,Reach-1,2
Up Type=0
Dn Type=3
Dn Slope=0.005
Boundary for River Rch & Prof#=Stream0025,Reach-1,3
Up Type=0
Dn Type=3
Dn Slope=0.005
Boundary for River Rch & Prof#=Stream0025,Reach-1,4
Up Type=0
Dn Type=3
Dn Slope=0.005
Boundary for River Rch & Prof#=Stream0025,Reach-1,5
Up Type=0
Dn Type=3
Dn Slope=0.005
Boundary for River Rch & Prof#=Stream0025,Reach-1,6
Up Type=0
Dn Type=3
Dn Slope=0.005
Boundary for River Rch & Prof#=Stream0025,Reach-1,7
Up Type=0
Dn Type=3
Dn Slope=0.005

--- Stream0025.g01 (geometry) ---

Geom Title=Existing Conditions
Program Version=4.10

River Reach=Stream0025      ,Reach-1
Reach XY= 30
        1970275.       13949225.      1970273.81     13949035.49
      1970229.19     13948973.26      1970218.88     13948922.82
      1970178.67     13948873.41      1970176.96     13948780.89
      1970466.86     13948481.06      1970520.84     13948373.28
      1970531.08      13948322.8      1970570.84     13948273.28
      1970581.08      13948222.8      1970620.84     13948173.28
      1970631.12     13948122.82      1970671.25     13948073.45
      1970677.26     13947880.94      1970721.14      13947823.4
      1970727.36     13947730.98      1970773.78      13947664.5
      1970778.54     13947476.46      1970973.97     13947264.56
      1970971.46     13947126.47      1970882.47     13947031.02
       1970876.5     13946980.87      1970918.57     13946933.04
      1970984.68     13946914.22      1971069.55     13946827.47
      1971078.75     13946576.55      1971118.88     13946527.18
      1971183.09     13946368.92        1971275.       13946275.

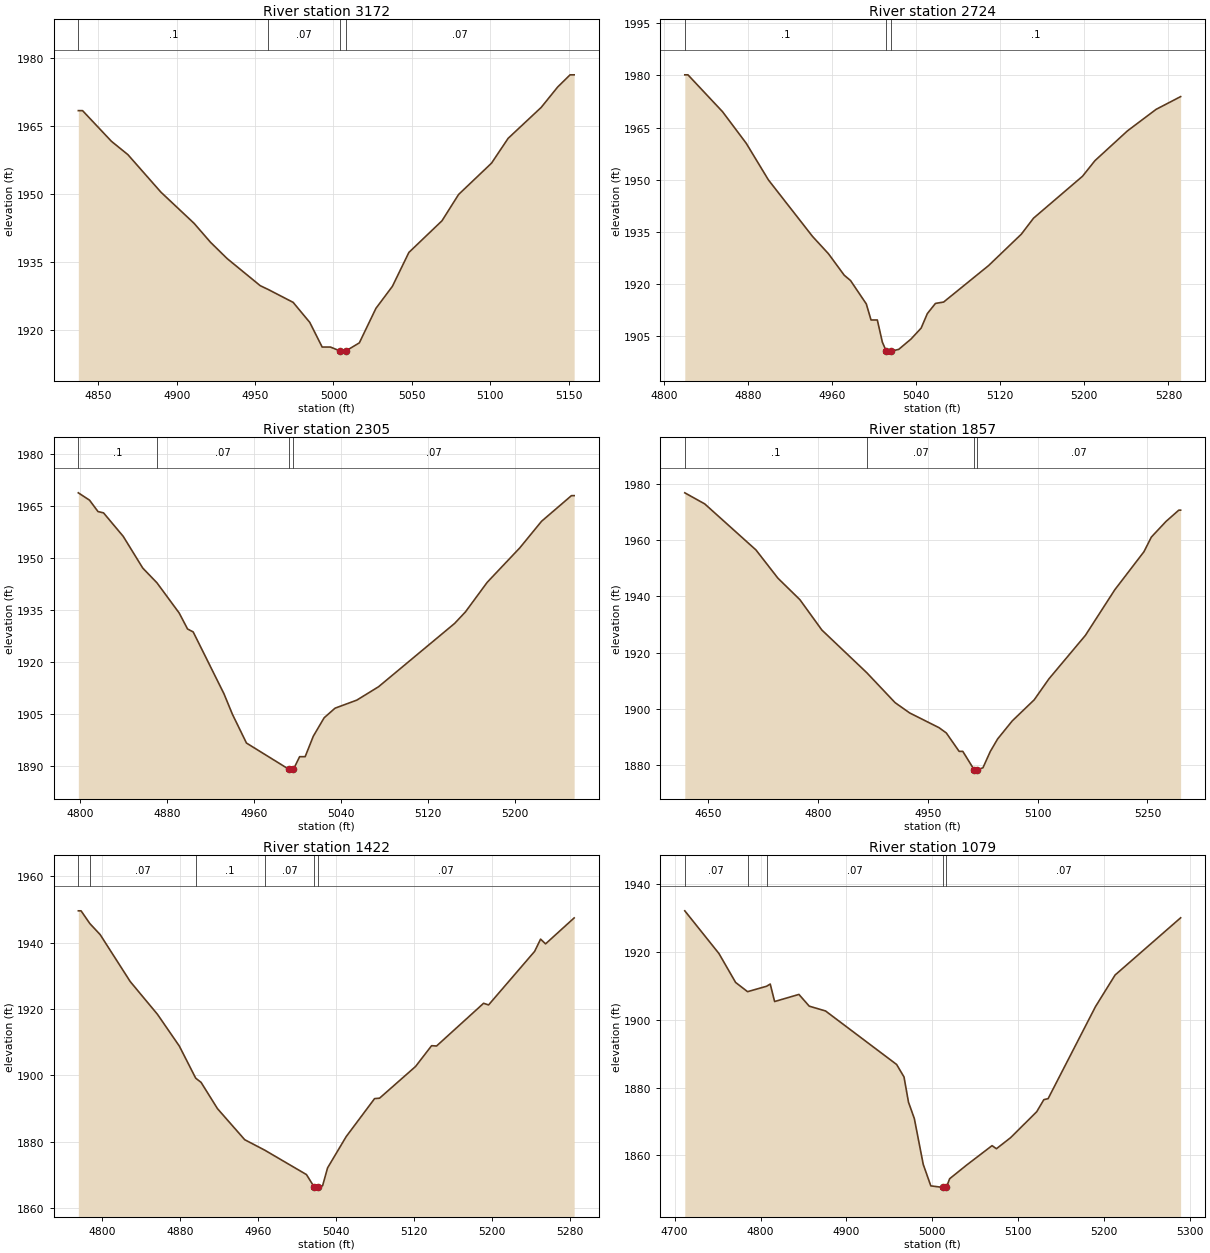
Type RM Length L Ch R = 1 ,3172    ,448,448,448
BEGIN DESCRIPTION:
Stream0025 7.0
END DESCRIPTION:
XS GIS Cut Line= 3
      1970375.02     13948874.99        1970225.       13948925.
      1970075.04     13948974.99
#Sta/Elev= 30
  4837.3 1968.37    4840 1968.37  4858.4 1961.62  4868.9 1958.68    4890  1950.4
  4911.1 1943.55  4921.6 1939.37  4932.2 1935.78  4953.3 1929.81  4958.4 1928.97
  4974.3 1926.13  4984.9 1921.72  4992.8 1916.29  4998.1 1916.29    5004 1915.45
  5004.2 1914.95  5007.7 1914.95    5008 1915.45  5016.5 1917.21  5027.1 1924.82
  5037.6 1929.67  5048.1 1937.13  5069.2  1944.1  5079.8  1949.9  5100.8  1956.8
  5111.4 1962.27  5132.5 1969.09    5143 1973.58  5150.9 1976.26  5153.5 1976.26
#Mann= 4 ,-1 , 0
  4837.3      .1       0  4958.4     .07       0    5004     .05       0
    5008     .07       0
Bank Sta=5004,5008
XS Rating Curve= 0 ,0
Exp/Cntr=0.3,0.1

Type RM Length L Ch R = 1 ,2724    ,419,419,419
BEGIN DESCRIPTION:
Stream0025 6.0
END DESCRIPTION:
XS GIS Cut Line= 3
      1970474.98     13948724.97        1970375.       13948575.
      1970224.99     13948324.99
#Sta/Elev= 30
  4819.8 1980.17  4822.8 1980.17  4855.8 1969.53  4878.3 1960.45  4899.4 1949.92
  4941.4 1933.65  4956.5 1928.69  4971.5 1922.51  4977.5 1920.98  4992.5 1914.25
    4997 1909.63    5003 1909.63  5007.8 1903.25  5011.6 1900.59  5011.9 1900.09
  5015.6 1900.59  5023.4 1901.18    5035 1904.13  5044.7  1907.3  5050.6 1911.47
  5058.3 1914.39  5066.1 1914.79  5108.9 1925.29    5140 1934.31  5151.6 1938.91
  5198.3    1951    5210 1955.45    5241 1964.04  5268.3 1970.24  5291.6  1973.9
#Mann= 3 ,-1 , 0
  4819.8      .1       0  5011.6     .05       0  5015.6      .1       0
Bank Sta=5011.6,5015.6
XS Rating Curve= 0 ,0
Exp/Cntr=0.3,0.1

Type RM Length L Ch R = 1 ,2305    ,448,448,448
BEGIN DESCRIPTION:
Stream0025 5.0
END DESCRIPTION:
XS GIS Cut Line= 3
      1970775.04     13948275.01        1970575.       13948225.
        1970325.       13948225.
#Sta/Elev= 30
  4798.4 1968.76  4808.7 1966.64  4816.5 1963.35  4821.6 1962.97  4839.7 1956.19
  4857.7 1947.02  4870.7 1942.79  4891.2 1934.05  4898.9 1929.44  4904.1 1928.58
  4932.4 1910.73  4940.2 1904.79  4953.1  1896.5  4992.3 1888.89  4992.5 1888.39
  4996.3 1888.89    5002 1892.56  5007.1 1892.56  5014.6 1898.48  5024.6 1903.81
  5034.6 1906.57  5054.6 1908.89  5074.6 1912.75  5144.6 1931.04  5154.6 1934.38
  5174.6 1942.92  5204.6 1952.87  5224.6 1960.54  5252.1 1967.95  5254.6 1967.95
#Mann= 4 ,-1 , 0
  4798.4      .1       0  4870.7     .07       0  4992.3     .05       0
  4996.3     .07       0
Bank Sta=4992.3,4996.3
XS Rating Curve= 0 ,0
Exp/Cntr=0.3,0.1

Type RM Length L Ch R = 1 ,1857    ,435,435,435
BEGIN DESCRIPTION:
Stream0025 4.0
END DESCRIPTION:
XS GIS Cut Line= 3
      1971102.22     13947829.24        1970725.       13947825.
      1970425.04       13947825.
#Sta/Elev= 30
  4618.1 1976.84  4645.3 1972.91  4715.3 1956.54  4745.3  1946.5  4775.3 1938.87
  4805.3 1928.08  4866.5 1912.95  4905.3 1902.27  4925.3  1898.6  4965.3 1893.38
  4975.3 1891.49  4992.8 1884.95  4997.8 1884.95  5013.3 1878.43  5013.6 1877.93
  5017.1 1877.93  5017.3 1878.43  5025.3 1879.11  5035.3 1884.89  5045.3 1889.34
  5065.3 1895.77  5095.3 1903.27  5115.3 1910.68  5165.3  1926.2  5205.3 1942.35
  5245.3 1955.94  5255.3 1961.11  5275.3 1966.66  5292.8 1970.68  5295.3 1970.68
#Mann= 4 ,-1 , 0
  4618.1      .1       0  4866.5     .07       0  5013.3     .05       0
  5017.3     .07       0
Bank Sta=5013.3,5017.3
XS Rating Curve= 0 ,0
Exp/Cntr=0.3,0.1

Type RM Length L Ch R = 1 ,1422    ,343,343,343
BEGIN DESCRIPTION:
Stream0025 3.0
END DESCRIPTION:
XS GIS Cut Line= 3
      1971025.04     13947525.02        1970825.       13947425.
      1970545.16     13947374.01
#Sta/Elev= 30
    4776 1949.62  4778.8 1949.62  4787.8 1945.78  4798.4 1942.44  4829.2 1928.29
  4857.1 1918.42  4879.5 1908.85  4896.3 1899.16  4901.8  1897.9  4918.6 1889.98
  4946.5 1880.62  4966.9 1877.49  5009.8  1870.1    5018 1866.22  5018.2 1865.72
    5022 1866.22  5026.3 1866.72  5031.4 1872.12  5050.5 1881.56  5079.6 1893.01
  5084.7 1893.14  5121.6  1902.7    5138 1908.96  5143.1 1908.87  5191.3 1921.75
  5196.4 1921.25  5243.6  1937.4  5249.7 1941.09  5254.8 1939.66  5284.1 1947.48
#Mann= 6 ,-1 , 0
    4776      .1       0  4787.8     .07       0  4896.3      .1       0
  4966.9     .07       0    5018     .05       0    5022     .07       0
Bank Sta=5018,5022
XS Rating Curve= 0 ,0
Exp/Cntr=0.3,0.1

Type RM Length L Ch R = 1 ,1079    ,558,558,558
BEGIN DESCRIPTION:
Stream0025 2.0
END DESCRIPTION:
XS GIS Cut Line= 3
      1971253.47     13947216.14      1970972.87     13947141.96
      1970689.77     13947093.83
#Sta/Elev= 30
  4711.8 1932.09  4751.6 1919.49    4771 1910.97  4784.9 1908.26    4807 1909.85
  4811.3 1910.51  4816.4 1905.35  4844.7 1907.45  4856.7 1903.99  4875.7 1902.57
  4958.5 1886.79  4967.1  1883.1  4972.3 1875.68  4979.1 1870.85  4989.5 1857.32
  4998.3 1851.01  5012.4 1850.55  5012.7 1850.05  5016.4 1850.55  5020.2 1853.11
  5040.4 1857.22  5069.6 1862.87  5074.7 1861.96  5091.2 1865.22  5121.6 1872.86
  5129.9 1876.42  5134.9 1876.73  5190.1 1903.87  5212.9 1913.17  5289.2 1930.03
#Mann= 5 ,-1 , 0
  4711.8     .07       0  4784.9      .1       0    4807     .07       0
  5012.4     .05       0  5016.4     .07       0
Bank Sta=5012.4,5016.4
XS Rating Curve= 0 ,0
Exp/Cntr=0.3,0.1

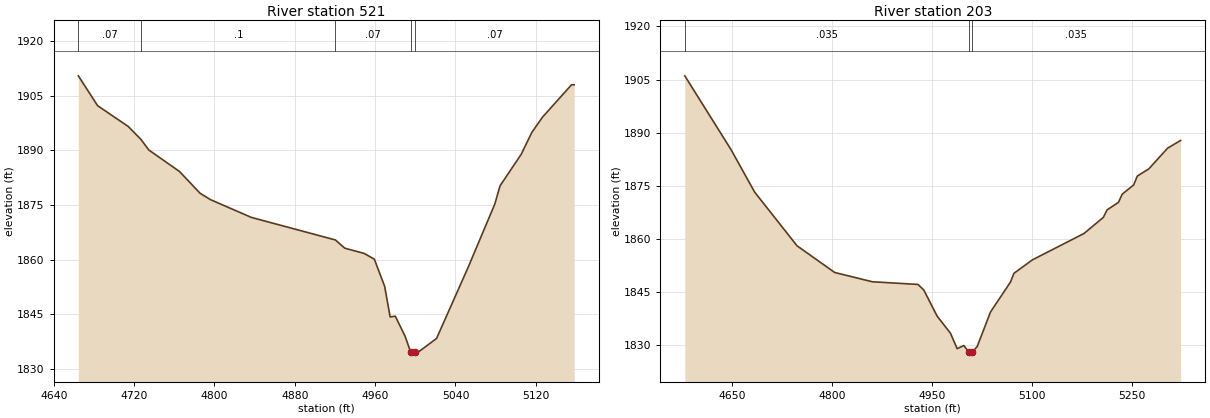
Type RM Length L Ch R = 1 ,521     ,318,318,318
BEGIN DESCRIPTION:
Stream0025 1.0
END DESCRIPTION:
XS GIS Cut Line= 3
      1971403.66     13946792.87        1971075.       13946725.
      1970925.01       13946675.
#Sta/Elev= 30
  4664.5 1910.44  4683.7 1902.25  4714.2 1896.54    4727 1892.95  4734.6 1890.11
  4765.2  1884.2  4785.7 1878.23  4795.9 1876.49  4836.7  1871.6  4920.5  1865.4
  4929.8 1863.15    4949 1861.72  4959.2 1860.15  4969.5  1852.7    4975 1844.27
  4980.1  1844.5  4989.9 1838.97  4995.5 1834.58  4995.8 1834.08  4999.5 1834.58
  5002.7 1834.58  5021.2 1838.38  5052.8    1858  5079.2 1875.26  5084.4 1880.26
  5105.5 1888.92    5116 1894.88  5126.6 1899.08  5155.6 1907.99  5158.2 1907.99
#Mann= 5 ,-1 , 0
  4664.5     .07       0    4727      .1       0  4920.5     .07       0
  4995.5     .05       0  4999.5     .07       0
Bank Sta=4995.5,4999.5
XS Rating Curve= 0 ,0
Exp/Cntr=0.3,0.1

Type RM Length L Ch R = 1 ,203     ,0,0,0
BEGIN DESCRIPTION:
Stream0025 0.0
END DESCRIPTION:
XS GIS Cut Line= 4
      1971483.17     13946685.11      1971237.21     13946441.16
      1971089.87     13946431.79      1970863.92      13946539.1
#Sta/Elev= 30
  4578.6 1906.05  4648.1  1885.2  4683.5 1873.23  4747.1  1858.1  4803.6 1850.57
  4860.2 1847.95  4928.6  1847.2  4937.3 1845.64  4957.3 1838.27  4977.3 1833.46
  4987.4 1829.08  4997.4 1829.96  5005.4 1828.04  5005.6 1827.54  5009.4 1828.04
  5017.4 1829.64  5037.5 1839.45  5067.5 1847.89  5072.6 1850.32  5100.2 1854.12
  5177.7 1861.56  5206.8 1866.12  5212.4 1868.22  5229.6 1870.38  5235.1 1872.66
  5252.3 1875.27  5257.8 1877.77    5275 1879.79  5303.3 1885.65  5322.8 1887.82
#Mann= 3 ,-1 , 0
  4578.6    .035       0  5005.4    .035       0  5009.4    .035       0
Bank Sta=5005.4,5009.4
XS Rating Curve= 0 ,0
Exp/Cntr=0.3,0.1

Chan Stop Cuts=-1
Use User Specified Reach Order=0
Composite Channel Slope=5