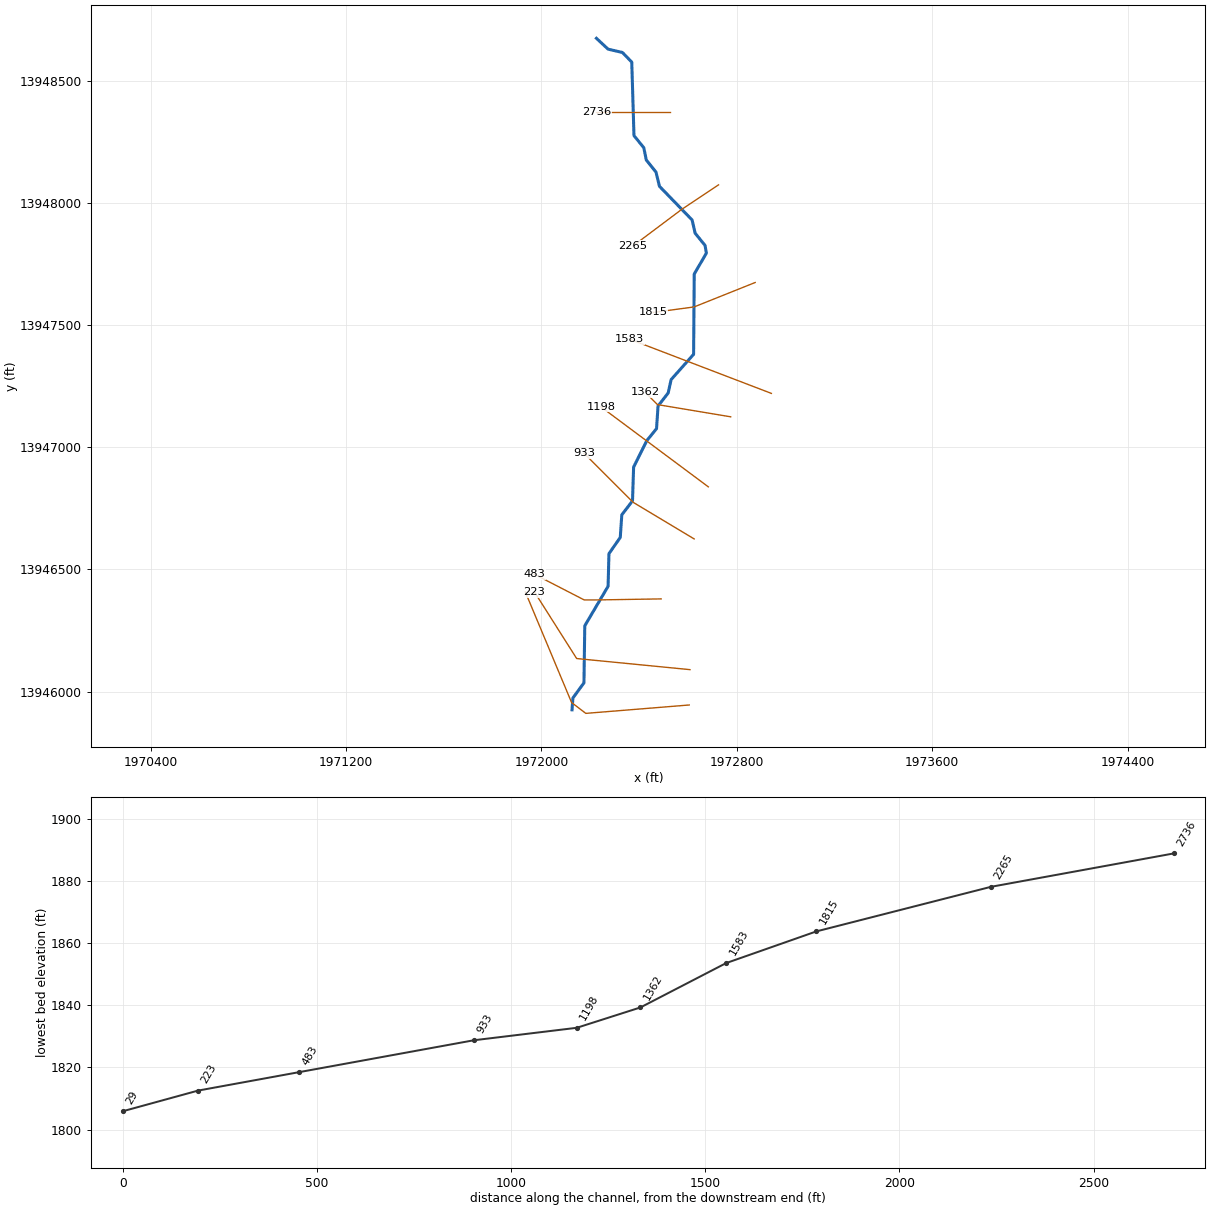
--- Stream0026.prj (project) ---

Proj Title=Stream0026 Base Level Engineering
Current Plan=p01
Default Exp/Contr=0.3,0.1
English Units
Geom File=g01
Flow File=f01
Plan File=p01
BEGIN DESCRIPTION:
Stream0026
END DESCRIPTION:

--- Stream0026.p01 (plan) ---

Plan Title=Multiple Run
Short Identifier=Multiple
Geom File=g01
Flow File=f01
Subcritical Flow
K Sum by GR= 0
Std Step Tol= 0.01
Critical Tol= 0.01
Num of Std Step Trials= 20
Max Error Tol= 0.3
Flow Tol Ratio= 0.001
Split Flow NTrial= 30
Split Flow Tol= 0.02
Split Flow Ratio= 0.02
Log Output Level= 0
Friction Slope Method= 1
Unsteady Friction Slope Method= 2
Unsteady Bridges Friction Slope Method= 1
Parabolic Critical Depth
Global Vel Dist=  1 , 1 , 1
Global Log Level= 0
CheckData=True
Encroach Param= -1, 0, 0, 0
BEGIN DESCRIPTION:
Multiple Run
END DESCRIPTION:

--- Stream0026.f01 (steady flow) ---

Flow Title=Multiple
Number of Profiles=7
Profile Names=10-year,25-year,50-year,1pct_min,100-year,1pct_plu,500-year
River Rch & RM= Stream0026,Reach-1,2736
     490     807    1101     732    1461    2915    2544
Boundary for River Rch & Prof#=Stream0026,Reach-1,1
Up Type=0
Dn Type=3
Dn Slope=0.005
Boundary for River Rch & Prof#=Stream0026,Reach-1,2
Up Type=0
Dn Type=3
Dn Slope=0.005
Boundary for River Rch & Prof#=Stream0026,Reach-1,3
Up Type=0
Dn Type=3
Dn Slope=0.005
Boundary for River Rch & Prof#=Stream0026,Reach-1,4
Up Type=0
Dn Type=3
Dn Slope=0.005
Boundary for River Rch & Prof#=Stream0026,Reach-1,5
Up Type=0
Dn Type=3
Dn Slope=0.005
Boundary for River Rch & Prof#=Stream0026,Reach-1,6
Up Type=0
Dn Type=3
Dn Slope=0.005
Boundary for River Rch & Prof#=Stream0026,Reach-1,7
Up Type=0
Dn Type=3
Dn Slope=0.005

--- Stream0026.g01 (geometry) ---

Geom Title=Existing Conditions

River Reach=Stream0026,Reach-1
Reach XY= 30
      1972225.00     13948675.00      1972272.68     13948630.72
      1972331.45     13948617.09      1972369.65     13948577.70
      1972378.75     13948276.55      1972418.88     13948227.18
      1972429.16     13948176.72      1972468.90     13948127.19
      1972483.14     13948068.94      1972616.86     13947931.06
      1972629.25     13947876.74      1972669.66     13947827.20
      1972675.29     13947795.18      1972625.54     13947709.79
      1972622.94     13947380.86      1972530.85     13947277.29
      1972518.86     13947222.83      1972477.33     13947169.03
      1972471.17     13947076.58      1972431.11     13947027.18
      1972377.25     13946919.07      1972372.73     13946780.94
      1972328.86     13946723.40      1972322.64     13946630.98
      1972276.23     13946564.49      1972272.75     13946430.93
      1972177.24     13946269.07      1972173.88     13946035.46
      1972128.65     13945973.49      1972125.00     13945925.00

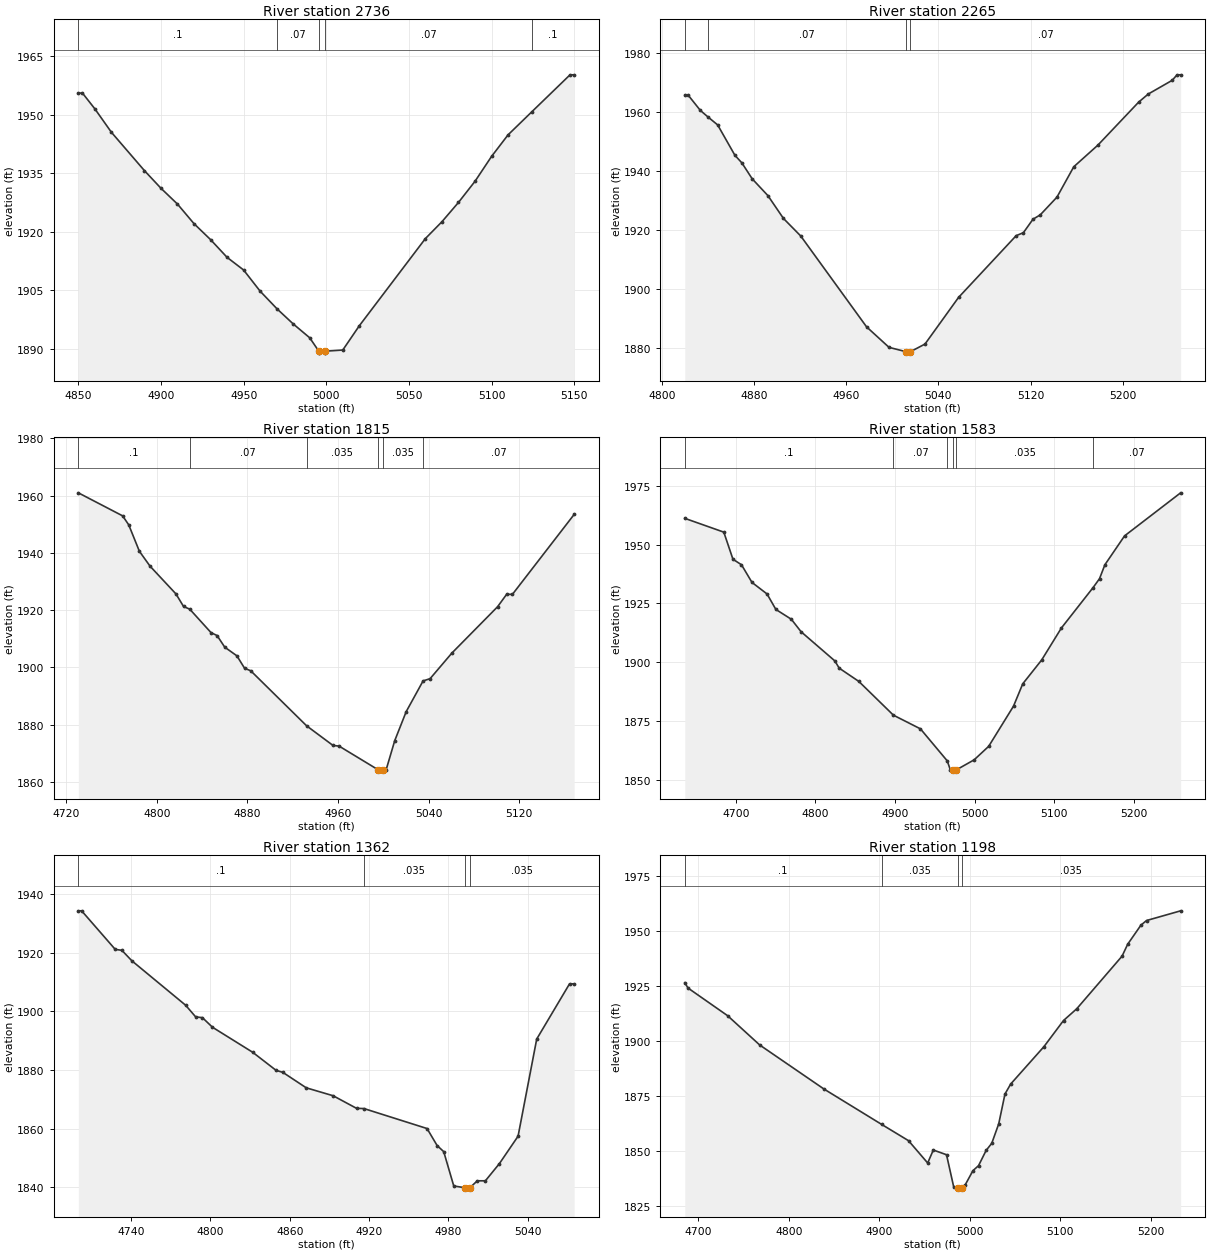
Type RM Length L Ch R = 1,2736,471,471,471
BEGIN DESCRIPTION:
Stream0026 6.0
END DESCRIPTION:
XS GIS Cut Line= 3
      1972525.02     13948375.00      1972375.00     13948375.00
      1972225.02     13948375.00
#Sta/Elev= 30
  4849.9 1955.56  4852.4 1955.56  4859.9 1951.52  4869.9 1945.52  4889.9 1935.68
  4899.9 1931.16  4909.9 1927.10  4919.9 1922.08  4929.9 1918.00  4939.9 1913.45
  4949.9 1910.21  4959.9 1904.78  4970.2 1900.22  4979.9 1896.39  4989.9 1892.83
  4995.4 1889.40  4995.7 1888.90  4999.2 1888.90  4999.4 1889.40  5009.9 1889.69
  5019.9 1895.91  5059.9 1918.27  5069.9 1922.58  5079.9 1927.53  5089.9 1932.94
  5099.9 1939.31  5109.9 1944.85  5124.3 1950.77  5147.4 1960.24  5149.9 1960.24
#Mann=5,-1,0
  4849.9     0.1       0  4970.2    0.07       0  4995.4    0.05       0
  4999.4    0.07       0  5124.3     0.1       0
Bank Sta=4995.4,4999.4
Exp/Cntr=0.3,0.1

Type RM Length L Ch R = 1,2265,450,450,450
BEGIN DESCRIPTION:
Stream0026 5.0
END DESCRIPTION:
XS GIS Cut Line= 3
      1972724.96     13948074.97      1972575.00     13947975.00
      1972375.03     13947825.02
#Sta/Elev= 30
  4820.0 1965.75  4823.0 1965.75  4833.5 1960.60  4840.4 1958.28  4848.5 1955.68
  4863.5 1945.34  4869.5 1942.79  4878.5 1937.35  4892.1 1931.66  4905.6 1923.90
  4920.6 1917.94  4977.7 1887.08  4997.2 1880.11  5011.8 1878.65  5012.0 1878.15
  5015.8 1878.65  5028.4 1881.23  5057.5 1897.06  5107.5 1918.05  5113.8 1919.07
  5122.1 1923.64  5128.4 1925.11  5142.9 1931.14  5157.5 1941.46  5178.4 1948.80
  5213.8 1963.42  5222.1 1966.16  5242.9 1970.83  5247.1 1972.69  5250.2 1972.69
#Mann=4,-1,0
  4820.0     0.1       0  4840.4    0.07       0  5011.8    0.05       0
  5015.8    0.07       0
Bank Sta=5011.8,5015.8
Exp/Cntr=0.3,0.1

Type RM Length L Ch R = 1,1815,232,232,232
BEGIN DESCRIPTION:
Stream0026 4.0
END DESCRIPTION:
XS GIS Cut Line= 3
      1972875.02     13947675.01      1972625.00     13947575.00
      1972458.00     13947552.42
#Sta/Elev= 30
  4730.7 1960.97  4769.8 1952.93  4775.2 1949.79  4784.6 1940.57  4794.0 1935.37
  4816.9 1925.67  4823.6 1921.29  4829.1 1920.34  4847.9 1912.14  4853.2 1911.14
  4860.0 1907.07  4870.7 1904.05  4877.5 1899.71  4882.9 1898.84  4932.3 1879.60
  4955.6 1872.75  4960.9 1872.54  4995.3 1864.29  4995.5 1863.79  4999.3 1864.29
  5002.5 1864.29  5010.1 1874.46  5020.2 1884.57  5035.1 1895.29  5041.3 1896.08
  5060.5 1905.00  5100.9 1921.20  5108.9 1925.54  5114.0 1925.52  5168.5 1953.43
#Mann=6,-1,0
  4730.7     0.1       0  4829.1    0.07       0  4932.3   0.035       0
  4995.3   0.035       0  4999.3   0.035       0  5035.1    0.07       0
Bank Sta=4995.3,4999.3
Exp/Cntr=0.3,0.1

Type RM Length L Ch R = 1,1583,221,221,221
BEGIN DESCRIPTION:
Mapping XS 22a94833
END DESCRIPTION:
XS GIS Cut Line= 2
      1972941.50     13947220.89      1972359.82     13947443.44
#Sta/Elev= 30
  4636.0 1961.19  4685.0 1955.32  4696.5 1943.77  4707.2 1941.44  4720.4 1933.92
  4739.3 1929.01  4750.4 1922.42  4769.8 1918.25  4782.1 1912.92  4824.5 1900.51
  4829.9 1897.45  4854.6 1891.79  4898.0 1877.43  4932.0 1871.60  4965.7 1857.96
  4969.4 1854.27  4972.9 1854.11  4973.1 1853.61  4976.9 1854.11  4999.5 1858.43
  5017.7 1864.16  5048.9 1881.27  5060.5 1890.77  5084.3 1900.93  5109.0 1914.51
  5148.8 1931.70  5156.9 1935.50  5163.7 1941.45  5188.4 1953.73  5258.8 1972.05
#Mann=6,-1,0
  4636.0     0.1       0  4898.0    0.07       0  4965.7   0.035       0
  4972.9   0.035       0  4976.9   0.035       0  5148.8    0.07       0
Bank Sta=4972.9,4976.9
Exp/Cntr=0.3,0.1

Type RM Length L Ch R = 1,1362,164,164,164
BEGIN DESCRIPTION:
Stream0026 3.0
END DESCRIPTION:
XS GIS Cut Line= 3
      1972774.98     13947125.00      1972475.00     13947175.00
      1972425.02     13947224.98
#Sta/Elev= 30
  4700.2 1934.35  4702.7 1934.35  4728.1 1921.18  4733.1 1920.87  4740.7 1917.27
  4781.3 1902.12  4788.9 1898.13  4794.0 1897.87  4801.6 1894.60  4832.0 1886.05
  4849.7 1879.87  4854.8 1879.19  4872.5 1873.91  4892.8 1871.21  4910.5 1866.91
  4916.1 1866.83  4963.8 1860.01  4971.4 1854.21  4976.4 1852.12  4984.0 1840.39
  4992.2 1839.82  4992.4 1839.32  4996.2 1839.82  5001.8 1842.16  5007.9 1842.16
  5018.5 1848.04  5032.6 1857.39  5046.7 1890.57  5071.5 1909.41  5075.0 1909.41
#Mann=4,-1,0
  4700.2     0.1       0  4916.1   0.035       0  4992.2   0.035       0
  4996.2   0.035       0
Bank Sta=4992.2,4996.2
Exp/Cntr=0.3,0.1

Type RM Length L Ch R = 1,1198,265,265,265
BEGIN DESCRIPTION:
Mapping XS 514cd8bd
END DESCRIPTION:
XS GIS Cut Line= 2
      1972683.21     13946838.18      1972243.85     13947165.54
#Sta/Elev= 30
  4685.1 1926.59  4688.6 1924.16  4732.4 1911.58  4767.9 1898.26  4838.8 1878.28
  4902.5 1862.21  4932.3 1854.79  4953.5 1844.64  4959.7 1850.54  4974.3 1848.40
  4982.2 1833.87  4986.9 1833.27  4987.2 1832.77  4990.9 1833.27  4995.1 1834.81
  5003.5 1841.16  5009.7 1843.44  5018.1 1850.38  5024.3 1853.59  5032.0 1862.44
  5038.9 1875.99  5045.2 1880.52  5081.9 1897.48  5103.6 1909.39  5118.2 1914.72
  5168.3 1938.64  5174.5 1944.05  5189.1 1952.70  5195.3 1954.82  5233.0 1959.23
#Mann=4,-1,0
  4685.1     0.1       0  4902.5   0.035       0  4986.9   0.035       0
  4990.9   0.035       0
Bank Sta=4986.9,4990.9
Exp/Cntr=0.3,0.1

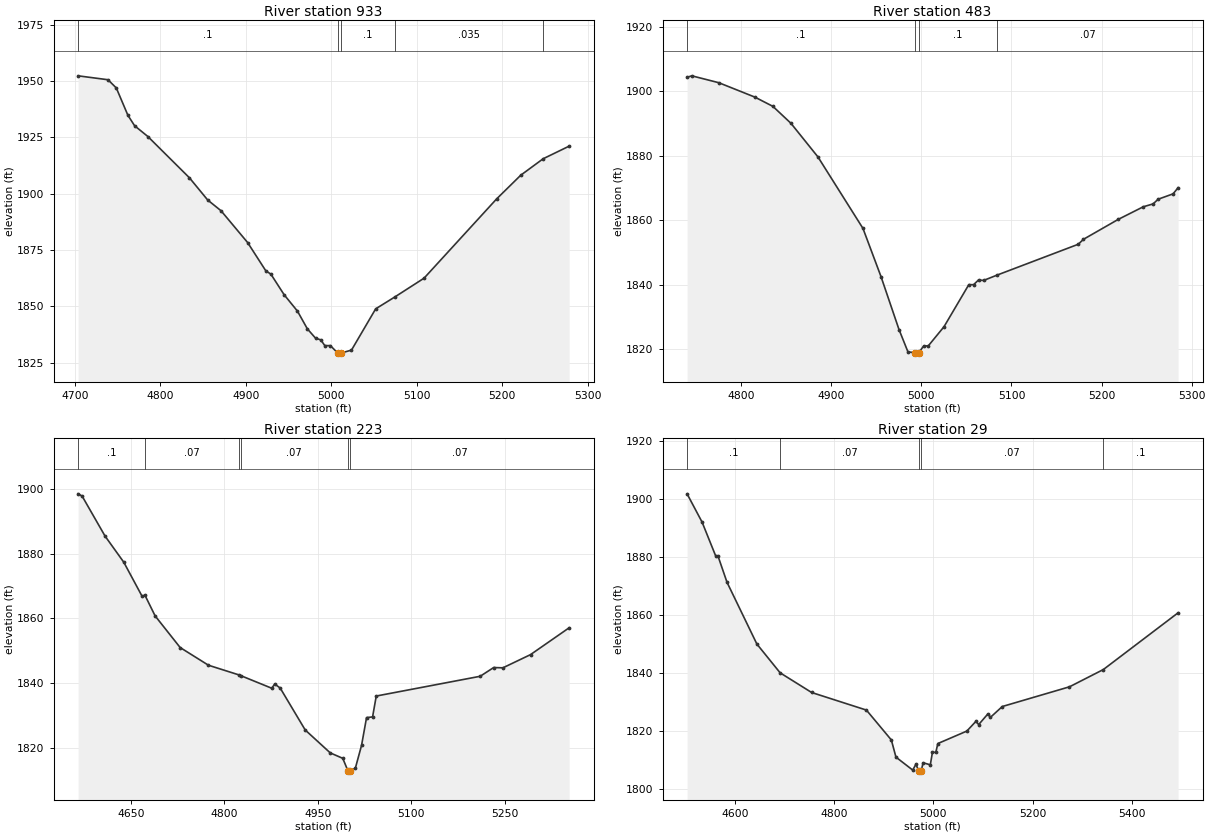
Type RM Length L Ch R = 1,933,450,450,450
BEGIN DESCRIPTION:
Stream0026 2.0
END DESCRIPTION:
XS GIS Cut Line= 3
      1972625.01     13946625.00      1972375.00     13946775.00
      1972175.00     13946975.00
#Sta/Elev= 30
  4703.9 1952.36  4738.9 1950.62  4748.6 1946.97  4762.2 1934.81  4770.0 1930.19
  4785.5 1925.41  4834.1 1907.09  4855.5 1897.21  4871.1 1892.44  4902.2 1878.32
  4923.5 1865.75  4929.4 1864.29  4944.9 1855.15  4960.5 1847.86  4972.1 1839.97
  4981.8 1835.79  4987.7 1835.12  4992.5 1832.54  4999.0 1832.54  5007.6 1829.26
  5007.8 1828.76  5011.6 1829.26  5023.7 1830.54  5052.0 1848.87  5074.5 1854.17
  5108.6 1862.49  5193.4 1897.67  5221.7 1908.22  5247.9 1915.53  5278.3 1921.13
#Mann=5,-1,0
  4703.9     0.1       0  5007.6    0.05       0  5011.6     0.1       0
  5074.5   0.035       0  5247.9    0.07       0
Bank Sta=5007.6,5011.6
Exp/Cntr=0.3,0.1

Type RM Length L Ch R = 1,483,260,260,260
BEGIN DESCRIPTION:
Stream0026 1.0
END DESCRIPTION:
XS GIS Cut Line= 4
      1972490.25     13946379.28      1972225.00     13946375.00
      1972175.00     13946375.00      1971970.62     13946480.31
#Sta/Elev= 30
  4739.8 1904.33  4745.1 1904.78  4775.1 1902.64  4815.1 1898.18  4835.1 1895.31
  4855.1 1890.07  4885.1 1879.64  4935.1 1857.47  4955.1 1842.55  4975.1 1826.13
  4985.1 1819.15  4993.1 1819.00  4993.3 1818.50  4997.1 1819.00  5002.6 1821.05
  5007.6 1821.05  5025.1 1827.01  5052.6 1840.03  5057.9 1840.03  5063.4 1841.49
  5069.0 1841.34  5083.8 1842.98  5174.2 1852.57  5179.8 1854.08  5218.5 1860.27
  5246.3 1864.18  5257.2 1865.07  5262.8 1866.52  5279.4 1868.19  5285.0 1870.10
#Mann=4,-1,0
  4739.8     0.1       0  4993.1    0.05       0  4997.1     0.1       0
  5083.8    0.07       0
Bank Sta=4993.1,4997.1
Exp/Cntr=0.3,0.1

Type RM Length L Ch R = 1,223,194,194,194
BEGIN DESCRIPTION:
Stream0026 0.1
END DESCRIPTION:
XS GIS Cut Line= 3
      1972608.08     13946089.55      1972143.98     13946135.04
      1971971.44     13946407.35
#Sta/Elev= 30
  4564.9 1898.49  4571.3 1897.81  4608.2 1885.44  4638.3 1877.37  4667.7 1866.86
  4672.2 1867.22  4688.6 1860.81  4728.8 1851.04  4774.3 1845.57  4822.7 1842.62
  4825.8 1842.39  4875.8 1838.48  4880.8 1839.76  4889.5 1838.53  4929.7 1825.58
  4969.9 1818.51  4990.0 1816.83  4998.1 1813.07  4998.3 1812.57  5002.1 1813.07
  5010.1 1813.70  5020.2 1820.85  5028.2 1829.40  5037.9 1829.62  5043.8 1836.06
  5210.7 1842.16  5232.4 1844.86  5247.2 1844.77  5291.6 1848.85  5353.6 1857.13
#Mann=6,-1,0
  4564.9     0.1       0  4672.2    0.07       0  4822.7     0.1       0
  4825.8    0.07       0  4998.1    0.05       0  5002.1    0.07       0
Bank Sta=4998.1,5002.1
Exp/Cntr=0.3,0.1

Type RM Length L Ch R = 1,29,0,0,0
BEGIN DESCRIPTION:
Stream0026 0.0
END DESCRIPTION:
XS GIS Cut Line= 4
      1972605.10     13945944.80      1972181.46     13945910.45
      1972123.16     13945955.04      1971933.75     13946407.78
#Sta/Elev= 30
  4503.8 1901.70  4534.0 1891.98  4561.1 1880.47  4566.2 1880.23  4584.2 1871.28
  4644.4 1850.01  4691.3 1840.09  4754.7 1833.33  4865.1 1827.27  4915.3 1816.99
  4924.6 1811.08  4958.4 1806.62  4964.7 1808.61  4970.5 1806.42  4970.9 1805.92
  4975.5 1806.42  4979.3 1809.15  4993.8 1808.43  4998.1 1812.74  5004.9 1812.74
  5009.0 1815.76  5067.4 1820.05  5085.8 1823.42  5091.2 1822.28  5109.6 1825.92
  5115.0 1824.79  5138.8 1828.50  5274.1 1835.28  5342.4 1841.23  5493.0 1860.76
#Mann=5,-1,0
  4503.8     0.1       0  4691.3    0.07       0  4970.5    0.05       0
  4975.5    0.07       0  5342.4     0.1       0
Bank Sta=4970.5,4975.5
Exp/Cntr=0.3,0.1

Chan Stop Cuts=-1