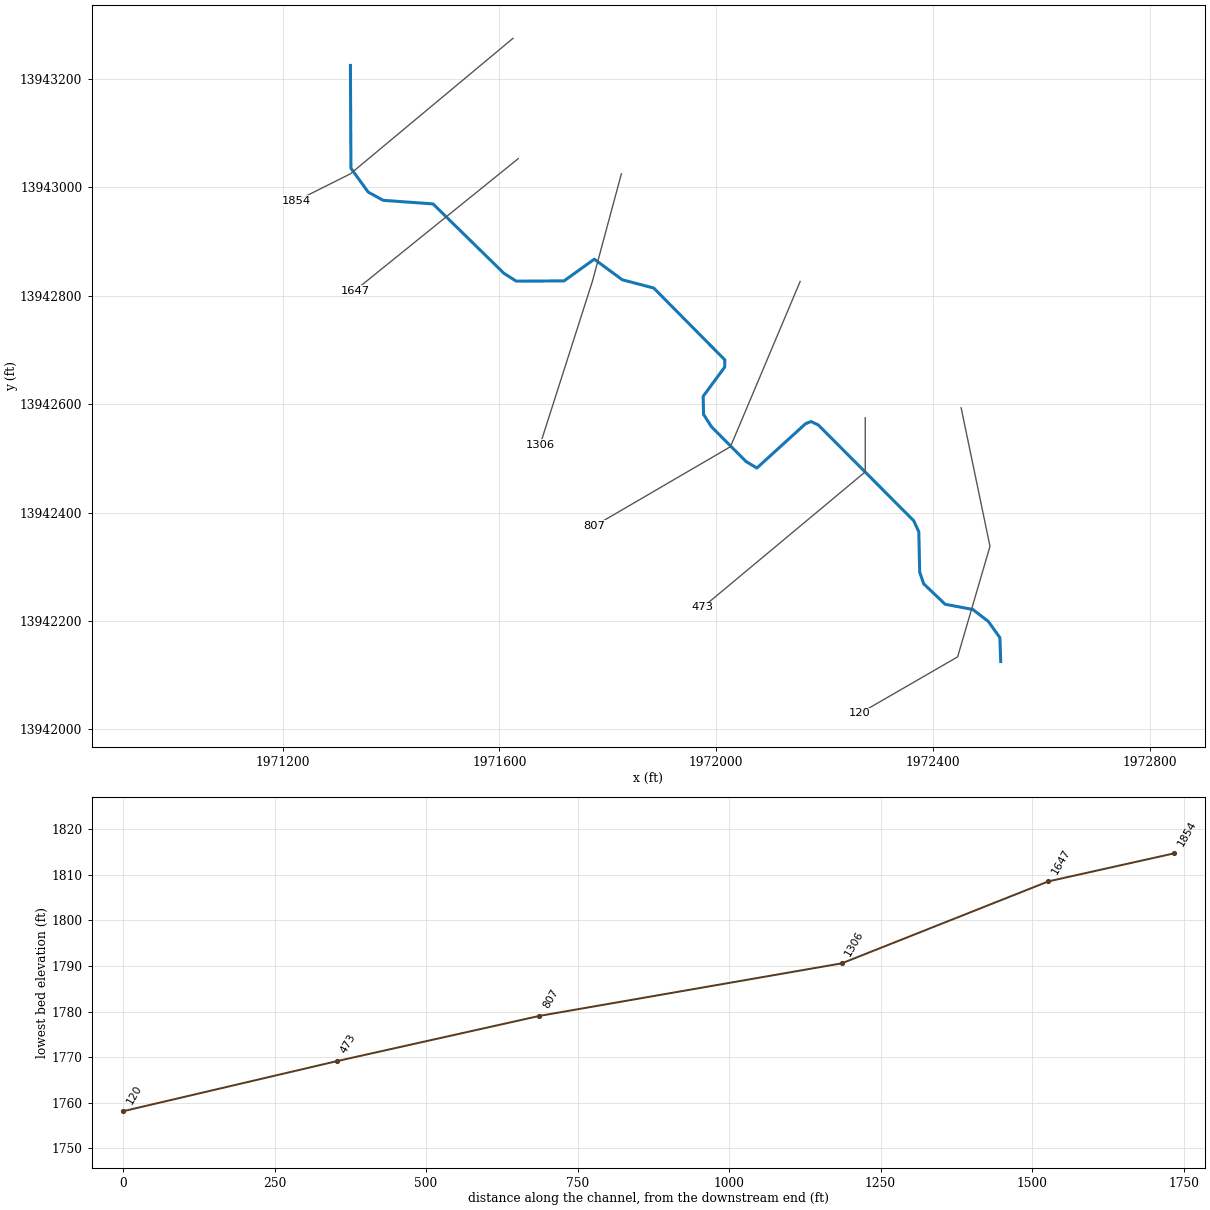
--- Stream0027.prj (project) ---

Proj Title=Stream0027 Base Level Engineering
Current Plan=p01
Default Exp/Contr=0.3,0.1
English Units
Geom File=g01
Flow File=f01
Plan File=p01
BEGIN DESCRIPTION:
Stream0027
END DESCRIPTION:

--- Stream0027.p01 (plan) ---

Plan Title=Multiple Run
Short Identifier=Multiple
Geom File=g01
Flow File=f01
Subcritical Flow
K Sum by GR= 0
Std Step Tol= 0.01
Critical Tol= 0.01
Num of Std Step Trials= 20
Max Error Tol= 0.3
Flow Tol Ratio= 0.001
Split Flow NTrial= 30
Split Flow Tol= 0.02
Split Flow Ratio= 0.02
Log Output Level= 0
Friction Slope Method= 1
Unsteady Friction Slope Method= 2
Unsteady Bridges Friction Slope Method= 1
Parabolic Critical Depth
Global Vel Dist=  1 , 1 , 1
Global Log Level= 0
CheckData=True
Encroach Param= -1, 0, 0, 0
BEGIN DESCRIPTION:
Multiple Run
END DESCRIPTION:

--- Stream0027.f01 (steady flow) ---

Flow Title=Multiple
Number of Profiles=7
Profile Names=10-year,25-year,50-year,1pct_min,100-year,1pct_plu,500-year
River Rch & RM= Stream0027,Reach-1,1854
     349     562     756     497     991    1977    1679
Boundary for River Rch & Prof#=Stream0027,Reach-1,1
Up Type=0
Dn Type=3
Dn Slope=0.005
Boundary for River Rch & Prof#=Stream0027,Reach-1,2
Up Type=0
Dn Type=3
Dn Slope=0.005
Boundary for River Rch & Prof#=Stream0027,Reach-1,3
Up Type=0
Dn Type=3
Dn Slope=0.005
Boundary for River Rch & Prof#=Stream0027,Reach-1,4
Up Type=0
Dn Type=3
Dn Slope=0.005
Boundary for River Rch & Prof#=Stream0027,Reach-1,5
Up Type=0
Dn Type=3
Dn Slope=0.005
Boundary for River Rch & Prof#=Stream0027,Reach-1,6
Up Type=0
Dn Type=3
Dn Slope=0.005
Boundary for River Rch & Prof#=Stream0027,Reach-1,7
Up Type=0
Dn Type=3
Dn Slope=0.005

--- Stream0027.g01 (geometry) ---

Geom Title=Existing Conditions

River Reach=Stream0027,Reach-1
Reach XY= 30
      1971325.00     13943225.00      1971325.97     13943035.26
      1971357.78     13942991.26      1971385.31     13942976.10
      1971477.42     13942969.47      1971608.25     13942841.40
      1971630.89     13942826.97      1971719.10     13942827.36
      1971775.01     13942867.47      1971826.65     13942829.45
      1971884.68     13942814.25      1972015.85     13942681.73
      1972015.67     13942668.45      1971975.89     13942614.36
      1971976.66     13942581.03      1971991.23     13942558.25
      1972054.95     13942494.20      1972074.99     13942482.09
      1972165.00     13942564.00      1972175.00     13942567.90
      1972188.33     13942561.58      1972364.48     13942384.78
      1972373.83     13942364.51      1972375.47     13942290.09
      1972382.75     13942268.55      1972422.43     13942230.72
      1972473.50     13942221.12      1972502.17     13942198.98
      1972523.44     13942169.13      1972525.00     13942125.00

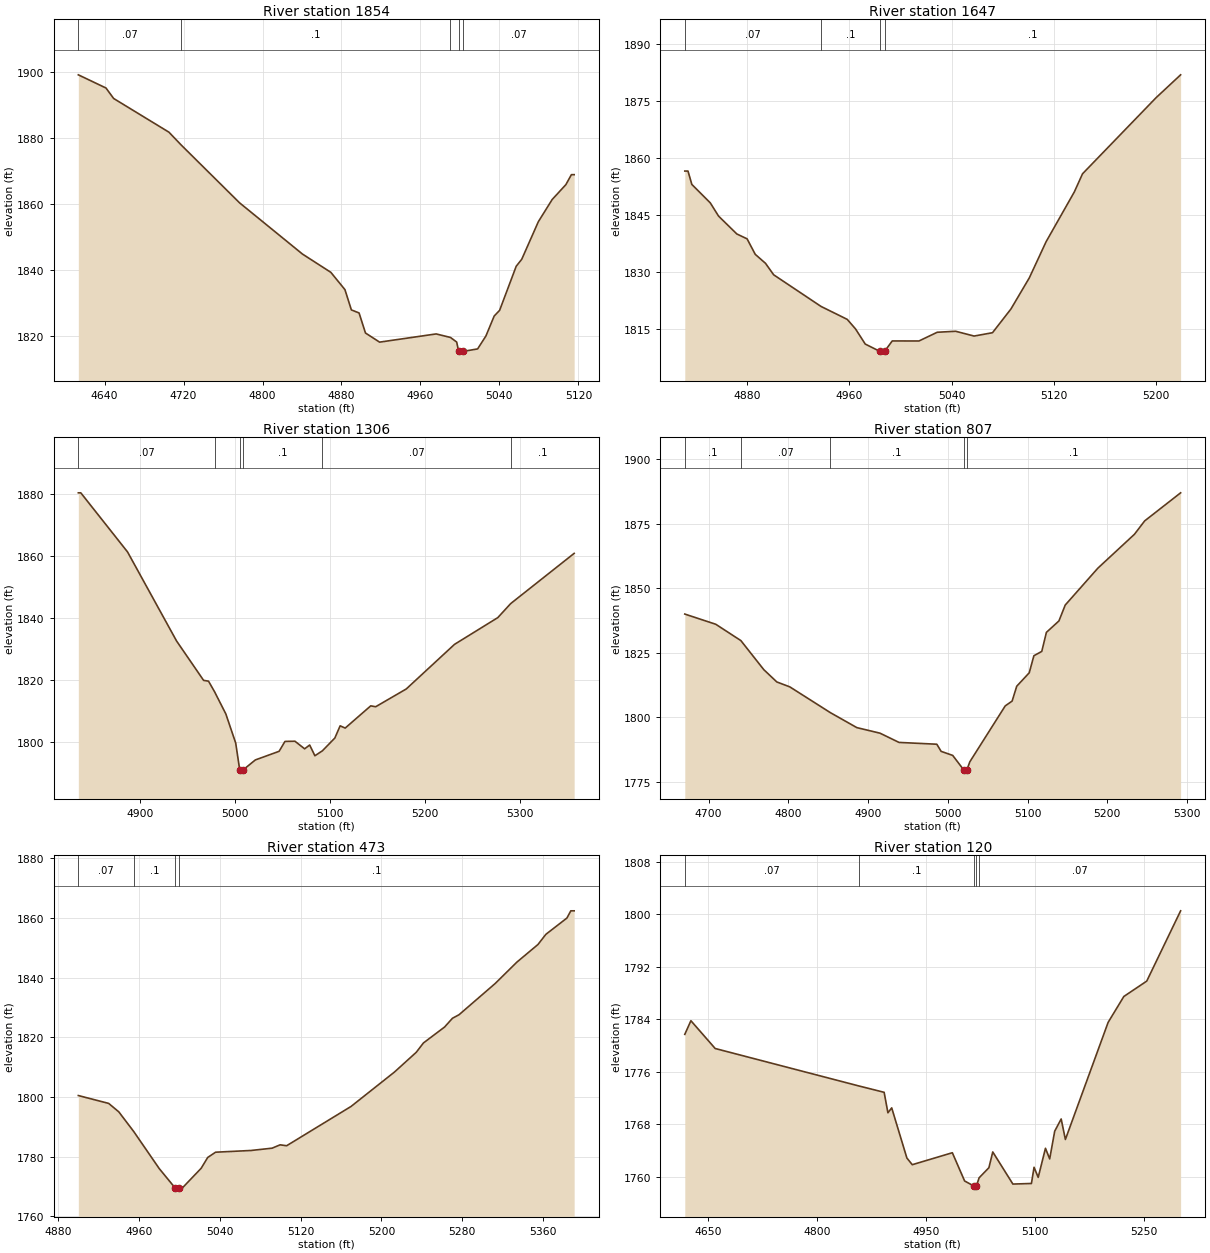
Type RM Length L Ch R = 1,1854,207,207,207
BEGIN DESCRIPTION:
Stream0027 4.0
END DESCRIPTION:
XS GIS Cut Line= 3
      1971625.00     13943275.00      1971325.00     13943025.00
      1971225.01     13942975.01
#Sta/Elev= 30
  4613.4 1899.20  4641.4 1895.20  4649.2 1892.01  4705.2 1881.78  4717.5 1877.92
  4776.8 1860.31  4840.5 1844.76  4869.2 1839.22  4883.5 1833.96  4890.0 1827.81
  4897.8 1826.88  4904.3 1820.79  4918.6 1818.02  4975.9 1820.51  4990.4 1819.44
  4996.7 1818.04  4998.7 1815.18  4998.9 1814.68  5002.7 1815.18  5017.9 1815.96
  5026.3 1819.88  5034.7 1825.95  5040.2 1827.68  5057.0 1841.07  5062.6 1843.18
  5079.4 1854.58  5093.4 1861.32  5107.3 1865.85  5112.9 1868.88  5115.7 1868.88
#Mann=5,-1,0
  4613.4    0.07       0  4717.5     0.1       0  4990.4    0.07       0
  4998.7    0.05       0  5002.7    0.07       0
Bank Sta=4998.7,5002.7
Exp/Cntr=0.3,0.1

Type RM Length L Ch R = 1,1647,341,341,341
BEGIN DESCRIPTION:
Mapping XS b4a61782
END DESCRIPTION:
XS GIS Cut Line= 2
      1971634.78     13943053.10      1971333.19     13942809.47
#Sta/Elev= 30
  4831.3 1856.53  4833.8 1856.53  4836.8 1853.01  4851.2 1848.16  4857.7 1844.66
  4872.0 1839.95  4880.0 1838.67  4886.4 1834.58  4894.4 1832.22  4900.8 1829.19
  4937.9 1820.84  4958.3 1817.45  4964.8 1814.93  4972.4 1810.94  4983.6 1809.05
  4983.8 1808.55  4987.6 1809.05  4993.5 1811.76  5014.4 1811.75  5028.7 1814.05
  5043.1 1814.31  5057.5 1813.05  5071.9 1813.93  5086.3 1820.17  5100.7 1828.39
  5113.8 1837.90  5135.9 1851.04  5142.3 1855.81  5199.8 1875.86  5219.0 1881.89
#Mann=4,-1,0
  4831.3    0.07       0  4937.9     0.1       0  4983.6    0.05       0
  4987.6     0.1       0
Bank Sta=4983.6,4987.6
Exp/Cntr=0.3,0.1

Type RM Length L Ch R = 1,1306,499,499,499
BEGIN DESCRIPTION:
Stream0027 3.0
END DESCRIPTION:
XS GIS Cut Line= 3
      1971824.99     13943024.98      1971771.50     13942826.54
      1971675.01     13942525.03
#Sta/Elev= 30
  4834.7 1880.32  4837.3 1880.32  4886.5 1861.27  4938.2 1832.52  4966.6 1819.85
  4971.8 1819.58  4978.1 1816.21  4990.0 1809.04  5000.4 1799.65  5004.6 1791.08
  5004.8 1790.58  5008.6 1791.08  5021.1 1794.19  5046.1 1796.97  5052.3 1800.16
  5062.8 1800.22  5073.0 1797.77  5078.3 1799.00  5083.8 1795.54  5091.7 1797.13
  5104.8 1801.25  5110.4 1805.19  5115.7 1804.46  5142.6 1811.63  5147.8 1811.34
  5180.0 1817.07  5230.8 1831.45  5276.4 1840.08  5290.0 1844.61  5356.8 1860.80
#Mann=6,-1,0
  4834.7    0.07       0  4978.1     0.1       0  5004.6    0.05       0
  5008.6     0.1       0  5091.7    0.07       0  5290.0     0.1       0
Bank Sta=5004.6,5008.6
Exp/Cntr=0.3,0.1

Type RM Length L Ch R = 1,807,334,334,334
BEGIN DESCRIPTION:
Stream0027 2.0
END DESCRIPTION:
XS GIS Cut Line= 3
      1972154.85     13942826.32      1972026.25     13942521.41
      1971775.01     13942375.01
#Sta/Elev= 30
  4670.2 1839.94  4709.0 1835.99  4740.5 1829.66  4769.3 1818.37  4785.6 1813.62
  4801.9 1811.71  4852.8 1801.71  4885.9 1795.92  4915.0 1793.76  4938.8 1790.18
  4986.2 1789.48  4991.6 1786.71  5006.1 1785.15  5019.9 1779.55  5020.1 1779.05
  5023.9 1779.55  5027.6 1782.67  5072.0 1804.35  5080.6 1806.19  5086.4 1811.96
  5102.1 1817.18  5107.9 1823.78  5117.8 1825.46  5123.6 1832.84  5139.3 1837.27
  5147.2 1843.43  5188.1 1857.72  5234.0 1870.87  5246.8 1876.05  5291.9 1886.94
#Mann=5,-1,0
  4670.2     0.1       0  4740.5    0.07       0  4852.8     0.1       0
  5019.9    0.05       0  5023.9     0.1       0
Bank Sta=5019.9,5023.9
Exp/Cntr=0.3,0.1

Type RM Length L Ch R = 1,473,353,353,353
BEGIN DESCRIPTION:
Stream0027 1.0
END DESCRIPTION:
XS GIS Cut Line= 3
      1972275.00     13942574.98      1972275.00     13942475.00
      1971974.99     13942224.99
#Sta/Elev= 30
  4900.1 1800.49  4930.1 1797.86  4940.1 1795.04  4954.9 1788.44  4980.1 1776.04
  4995.6 1769.64  4995.8 1769.14  4999.6 1769.64  5003.3 1769.64  5021.6 1776.12
  5028.1 1779.75  5035.9 1781.51  5071.0 1782.09  5091.8 1782.86  5099.7 1783.98
  5106.2 1783.68  5169.9 1796.84  5212.9 1808.38  5234.4 1814.98  5241.5 1818.11
  5262.4 1823.44  5270.2 1826.37  5276.7 1827.56  5312.5 1838.03  5334.0 1845.20
  5354.8 1851.09  5362.6 1854.49  5383.4 1859.94  5387.3 1862.37  5390.6 1862.37
#Mann=4,-1,0
  4900.1    0.07       0  4954.9     0.1       0  4995.6    0.05       0
  4999.6     0.1       0
Bank Sta=4995.6,4999.6
Exp/Cntr=0.3,0.1

Type RM Length L Ch R = 1,120,0,0,0
BEGIN DESCRIPTION:
Stream0027 0.0
END DESCRIPTION:
XS GIS Cut Line= 4
      1972451.93     13942593.18      1972505.17     13942337.64
      1972445.45     13942133.61      1972265.02     13942029.37
#Sta/Elev= 30
  4618.3 1781.71  4626.7 1783.79  4660.1 1779.56  4858.3 1773.84  4892.5 1772.89
  4897.7 1769.77  4902.9 1770.52  4923.8 1762.88  4931.2 1761.87  4986.3 1763.69
  5003.2 1759.39  5015.5 1758.65  5015.8 1758.15  5019.5 1758.65  5023.1 1759.87
  5036.6 1761.41  5041.9 1763.81  5069.6 1758.92  5095.1 1759.01  5098.7 1761.48
  5104.4 1759.94  5114.4 1764.37  5120.2 1762.75  5127.1 1766.97  5136.0 1768.83
  5141.8 1765.71  5200.6 1783.54  5222.2 1787.48  5253.7 1789.82  5300.3 1800.52
#Mann=5,-1,0
  4618.3    0.07       0  4858.3     0.1       0  5015.5    0.05       0
  5019.5     0.1       0  5023.1    0.07       0
Bank Sta=5015.5,5019.5
Exp/Cntr=0.3,0.1

Chan Stop Cuts=-1