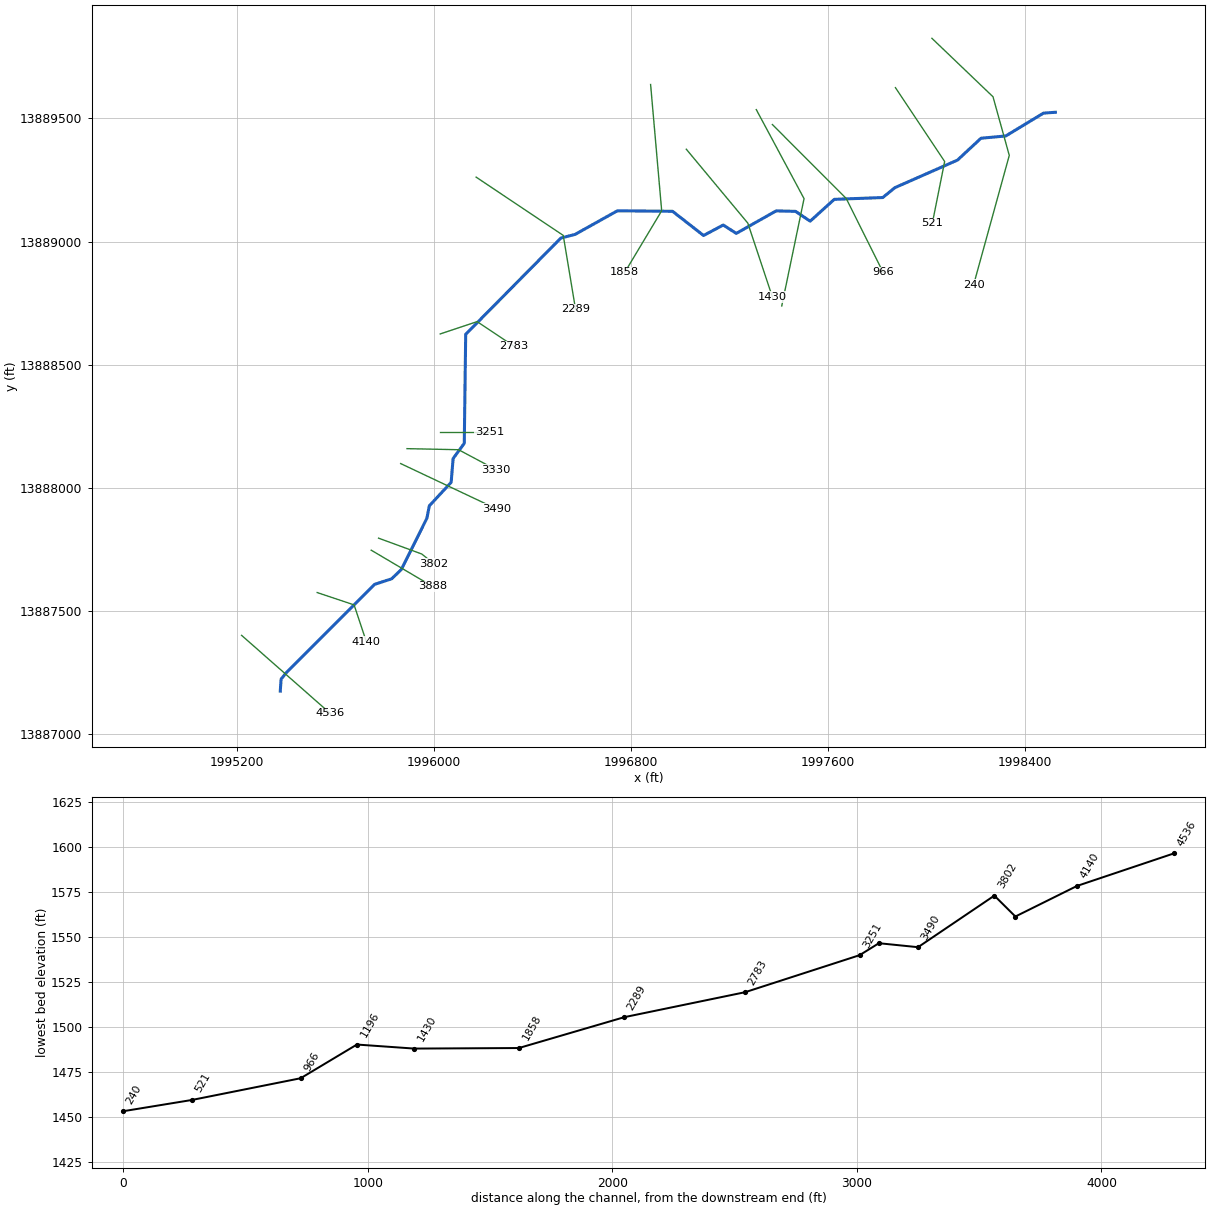
--- Stream0028.prj (project) ---

Proj Title=Stream0028 Base Level Engineering
Current Plan=p01
Default Exp/Contr=0.3,0.1
English Units
Geom File=g01
Flow File=f01
Plan File=p01
Y Axis Title=Elevation
X Axis Title(PF)=Main Channel Distance
X Axis Title(XS)=Station
BEGIN DESCRIPTION:
Stream0028
END DESCRIPTION:
DSS Export Rating Curves= 0
DSS Export Rating Curve Sorted= 0
DSS Export Volume Flow Curves= 0
DXF OffsetX= 0
DXF OffsetY= 0
DXF ScaleX= 1
DXF ScaleY= 10

--- Stream0028.p01 (plan) ---

Plan Title=Multiple Run
Short Identifier=Multiple
Geom File=g01
Flow File=f01
Subcritical Flow
K Sum by GR= 0
Std Step Tol= 0.01
Critical Tol= 0.01
Num of Std Step Trials= 20
Max Error Tol= 0.3
Flow Tol Ratio= 0.001
Split Flow NTrial= 30
Split Flow Tol= 0.02
Split Flow Ratio= 0.02
Log Output Level= 0
Friction Slope Method= 1
Unsteady Friction Slope Method= 2
Unsteady Bridges Friction Slope Method= 1
Parabolic Critical Depth
Global Vel Dist=  1 , 1 , 1
Global Log Level= 0
CheckData=True
Encroach Param= -1, 0, 0, 0
BEGIN DESCRIPTION:
Multiple Run
END DESCRIPTION:

--- Stream0028.f01 (steady flow) ---

Flow Title=Multiple
Number of Profiles=7
Profile Names=10-year,25-year,50-year,1pct_min,100-year,1pct_plu,500-year
River Rch & RM= Stream0028,Reach-1,4536
     185     281     364     231     461     919     723
River Rch & RM= Stream0028,Reach-1,3888
     726    1219    1686    1134    2262    4513    4022
Boundary for River Rch & Prof#=Stream0028,Reach-1,1
Up Type=0
Dn Type=3
Dn Slope=0.005
Boundary for River Rch & Prof#=Stream0028,Reach-1,2
Up Type=0
Dn Type=3
Dn Slope=0.005
Boundary for River Rch & Prof#=Stream0028,Reach-1,3
Up Type=0
Dn Type=3
Dn Slope=0.005
Boundary for River Rch & Prof#=Stream0028,Reach-1,4
Up Type=0
Dn Type=3
Dn Slope=0.005
Boundary for River Rch & Prof#=Stream0028,Reach-1,5
Up Type=0
Dn Type=3
Dn Slope=0.005
Boundary for River Rch & Prof#=Stream0028,Reach-1,6
Up Type=0
Dn Type=3
Dn Slope=0.005
Boundary for River Rch & Prof#=Stream0028,Reach-1,7
Up Type=0
Dn Type=3
Dn Slope=0.005

--- Stream0028.g01 (geometry) ---

Geom Title=Existing Conditions
Program Version=4.10

River Reach=Stream0028      ,Reach-1
Reach XY= 30
        1995375.       13887175.      1995378.27     13887223.64
      1995401.35      13887251.8      1995758.34     13887608.34
      1995827.54     13887630.75      1995866.98     13887668.66
      1995970.81     13887876.74      1995980.85     13887927.29
      1996069.46     13888022.58      1996077.36     13888119.02
      1996122.74     13888180.94      1996128.54     13888623.54
      1996515.32     13889014.24      1996573.26     13889029.19
      1996745.03     13889124.94      1996969.14     13889122.93
      1997095.16     13889024.68      1997175.08     13889067.17
      1997228.23     13889033.24      1997390.27     13889124.63
      1997469.11     13889122.63      1997528.41     13889082.81
      1997626.46     13889171.44      1997823.45     13889178.75
      1997872.82     13889218.88      1998127.29     13889330.85
      1998222.58     13889419.46      1998323.41     13889428.83
      1998476.49      13889521.4        1998525.       13889525.

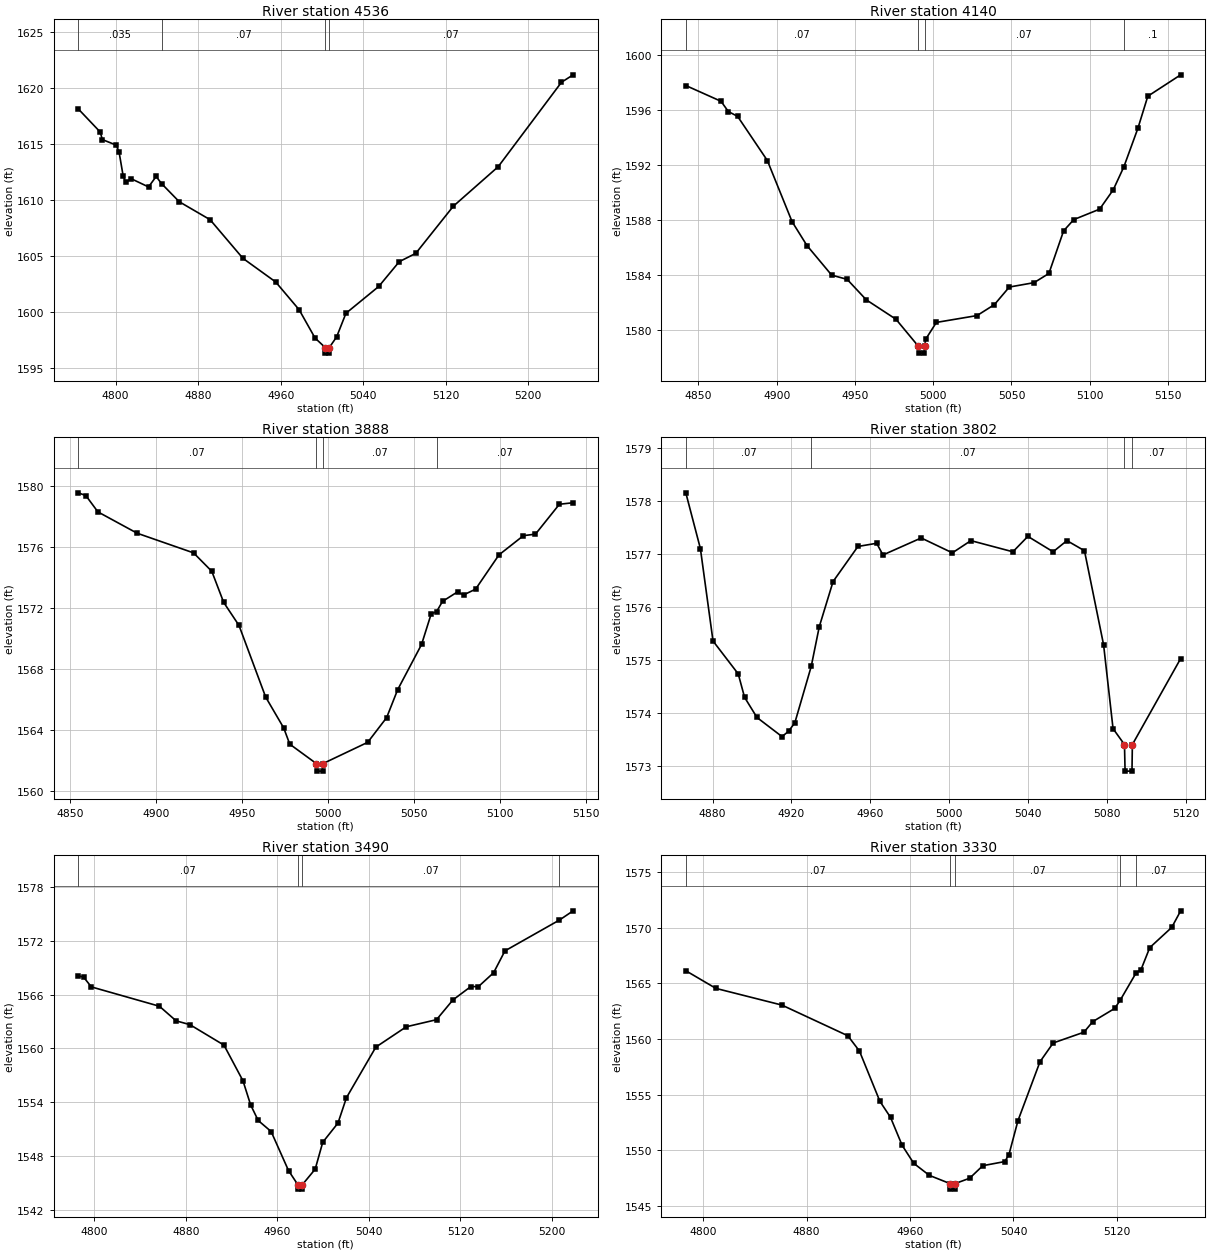
Type RM Length L Ch R = 1 ,4536    ,396,396,396
BEGIN DESCRIPTION:
Stream0028 10.0
END DESCRIPTION:
XS GIS Cut Line= 2
       1995217.7     13887401.37      1995577.98      13887084.5
#Sta/Elev= 30
  4763.8 1618.11  4785.1 1616.05  4787.1 1615.38  4800.8 1614.88  4803.4 1614.24
  4807.3 1612.14  4809.8 1611.56  4814.9  1611.9  4831.9 1611.16  4839.3 1612.09
  4844.5 1611.46  4861.7 1609.84  4891.6 1608.24  4923.4  1604.8  4955.2 1602.69
  4977.9 1600.22  4993.4 1597.69  5003.2 1596.85  5003.4 1596.35  5006.9 1596.35
  5007.2 1596.85  5014.3  1597.8  5023.3  1599.9  5055.1 1602.29    5075  1604.5
    5091 1605.24  5127.4 1609.44  5170.9 1612.96  5232.3 1620.49  5243.6 1621.15
#Mann= 4 ,-1 , 0
  4763.8    .035       0  4844.5     .07       0  5003.2     .05       0
  5007.2     .07       0
Bank Sta=5003.2,5007.2
XS Rating Curve= 0 ,0
Exp/Cntr=0.3,0.1

Type RM Length L Ch R = 1 ,4140    ,252,252,252
BEGIN DESCRIPTION:
Stream0028 9.0
END DESCRIPTION:
XS GIS Cut Line= 3
      1995524.98     13887575.01        1995675.       13887525.
      1995724.98     13887375.05
#Sta/Elev= 30
  4841.9 1597.81  4864.4 1596.66  4869.1 1595.91    4875 1595.56    4894 1592.34
  4909.8 1587.88  4919.3 1586.14  4935.1 1583.98    4945 1583.67  4957.2 1582.18
  4976.2 1580.76  4990.5 1578.79  4990.7 1578.29  4994.2 1578.29  4994.5 1578.79
  4995.2 1579.31    5002 1580.53    5028 1581.03  5039.1 1581.83  5048.6 1583.11
  5064.4 1583.43  5073.9  1584.1  5083.3 1587.21  5089.8 1588.03  5106.3 1588.79
    5115  1590.2  5121.8 1591.88  5130.8  1594.7  5137.1 1597.03  5158.1 1598.59
#Mann= 4 ,-1 , 0
  4841.9     .07       0  4990.5     .05       0  4994.5     .07       0
  5121.8      .1       0
Bank Sta=4990.5,4994.5
XS Rating Curve= 0 ,0
Exp/Cntr=0.3,0.1

Type RM Length L Ch R = 1 ,3888    ,86,86,86
BEGIN DESCRIPTION:
Mapping XS f3706f06
END DESCRIPTION:
XS GIS Cut Line= 2
      1995744.59     13887747.03      1995992.27     13887600.85
#Sta/Elev= 30
  4854.8 1579.57  4859.2 1579.39  4866.2 1578.32    4889 1576.92  4921.8 1575.63
  4932.4 1574.42  4939.3 1572.38  4948.2 1570.87  4963.7 1566.17  4974.2 1564.14
  4977.7 1563.08  4993.1 1561.81  4993.3 1561.31  4996.8 1561.31  4997.1 1561.81
    5023  1563.2    5034 1564.82  5040.4 1566.65  5054.3 1569.62  5059.9 1571.63
    5063 1571.77  5066.5 1572.45  5075.2 1573.07  5078.7 1572.87  5085.7 1573.25
  5099.3  1575.5  5113.5 1576.76  5120.5 1576.86  5134.4 1578.82  5142.4 1578.92
#Mann= 4 ,-1 , 0
  4854.8     .07       0  4993.1     .05       0  4997.1     .07       0
    5063     .07       0
Bank Sta=4993.1,4997.1
XS Rating Curve= 0 ,0
Exp/Cntr=0.3,0.1

Type RM Length L Ch R = 1 ,3802    ,312,312,312
BEGIN DESCRIPTION:
Stream0028 9.1
END DESCRIPTION:
XS GIS Cut Line= 3
      1995774.46     13887795.85      1995949.78     13887731.62
      1996000.15     13887691.67
#Sta/Elev= 30
  4866.4 1578.15  4873.8  1577.1  4880.2 1575.36    4893 1574.74  4896.2  1574.3
  4902.5 1573.92  4915.2 1573.56  4918.5 1573.66  4921.7 1573.82    4930 1574.88
  4934.1 1575.63  4941.1 1576.48  4953.7 1577.14  4963.2  1577.2  4966.4 1576.98
  4985.8  1577.3  5001.6 1577.02    5011 1577.25  5032.3 1577.04  5039.9 1577.33
  5052.7 1577.04  5059.7 1577.25  5068.6 1577.06  5078.3 1575.29  5083.1 1573.71
  5088.9 1573.41  5089.2 1572.91  5092.7 1572.91  5092.9 1573.41  5117.4 1575.03
#Mann= 4 ,-1 , 0
  4866.4     .07       0    4930     .07       0  5088.9     .05       0
  5092.9     .07       0
Bank Sta=5088.9,5092.9
XS Rating Curve= 0 ,0
Exp/Cntr=0.3,0.1

Type RM Length L Ch R = 1 ,3490    ,160,160,160
BEGIN DESCRIPTION:
Mapping XS 77bb3e9a
END DESCRIPTION:
XS GIS Cut Line= 2
      1995864.25     13888098.68      1996255.27      13887914.1
#Sta/Elev= 30
  4786.1 1568.08  4790.7 1567.95  4797.5 1566.85    4857 1564.69  4871.6 1563.06
  4883.6 1562.64  4913.4 1560.35    4930 1556.37  4936.7 1553.68  4943.3 1551.94
  4954.6 1550.71  4969.8 1546.35  4977.9 1544.78  4978.1 1544.28  4981.6 1544.28
  4981.9 1544.78  4993.1 1546.51  4999.7 1549.51    5013 1551.65  5020.4 1554.48
  5046.1 1560.13  5072.7  1562.4  5099.1 1563.19  5113.4 1565.39  5129.1 1566.89
  5135.7 1566.88    5149 1568.43  5158.9 1570.87  5206.5 1574.31  5218.5 1575.34
#Mann= 4 ,-1 , 0
  4786.1     .07       0  4977.9     .05       0  4981.9     .07       0
  5206.5    .035       0
Bank Sta=4977.9,4981.9
XS Rating Curve= 0 ,0
Exp/Cntr=0.3,0.1

Type RM Length L Ch R = 1 ,3330    ,79,79,79
BEGIN DESCRIPTION:
Stream0028 7.1
END DESCRIPTION:
XS GIS Cut Line= 3
      1995890.11     13888159.29       1996099.5     13888154.95
      1996252.47     13888073.59
#Sta/Elev= 30
  4786.6 1566.14  4809.9 1564.55  4860.9 1563.05  4911.9 1560.29  4920.9 1558.91
  4936.7 1554.39  4944.9 1552.95  4953.9 1550.43  4962.9 1548.81  4974.9 1547.73
  4990.9 1546.99  4991.2 1546.49  4994.7 1546.49  4994.9 1546.99  5006.1 1547.47
  5016.3  1548.6  5033.3 1548.97  5036.5  1549.6  5043.5 1552.66  5060.5 1557.95
  5070.7 1559.64  5094.5 1560.61  5101.3 1561.56  5118.3 1562.75  5122.6  1563.5
  5134.8 1565.94  5138.6 1566.23  5145.4 1568.22  5162.4 1570.04  5169.3 1571.53
#Mann= 5 ,-1 , 0
  4786.6     .07       0  4990.9     .05       0  4994.9     .07       0
  5122.6    .035       0  5134.8     .07       0
Bank Sta=4990.9,4994.9
XS Rating Curve= 0 ,0
Exp/Cntr=0.3,0.1

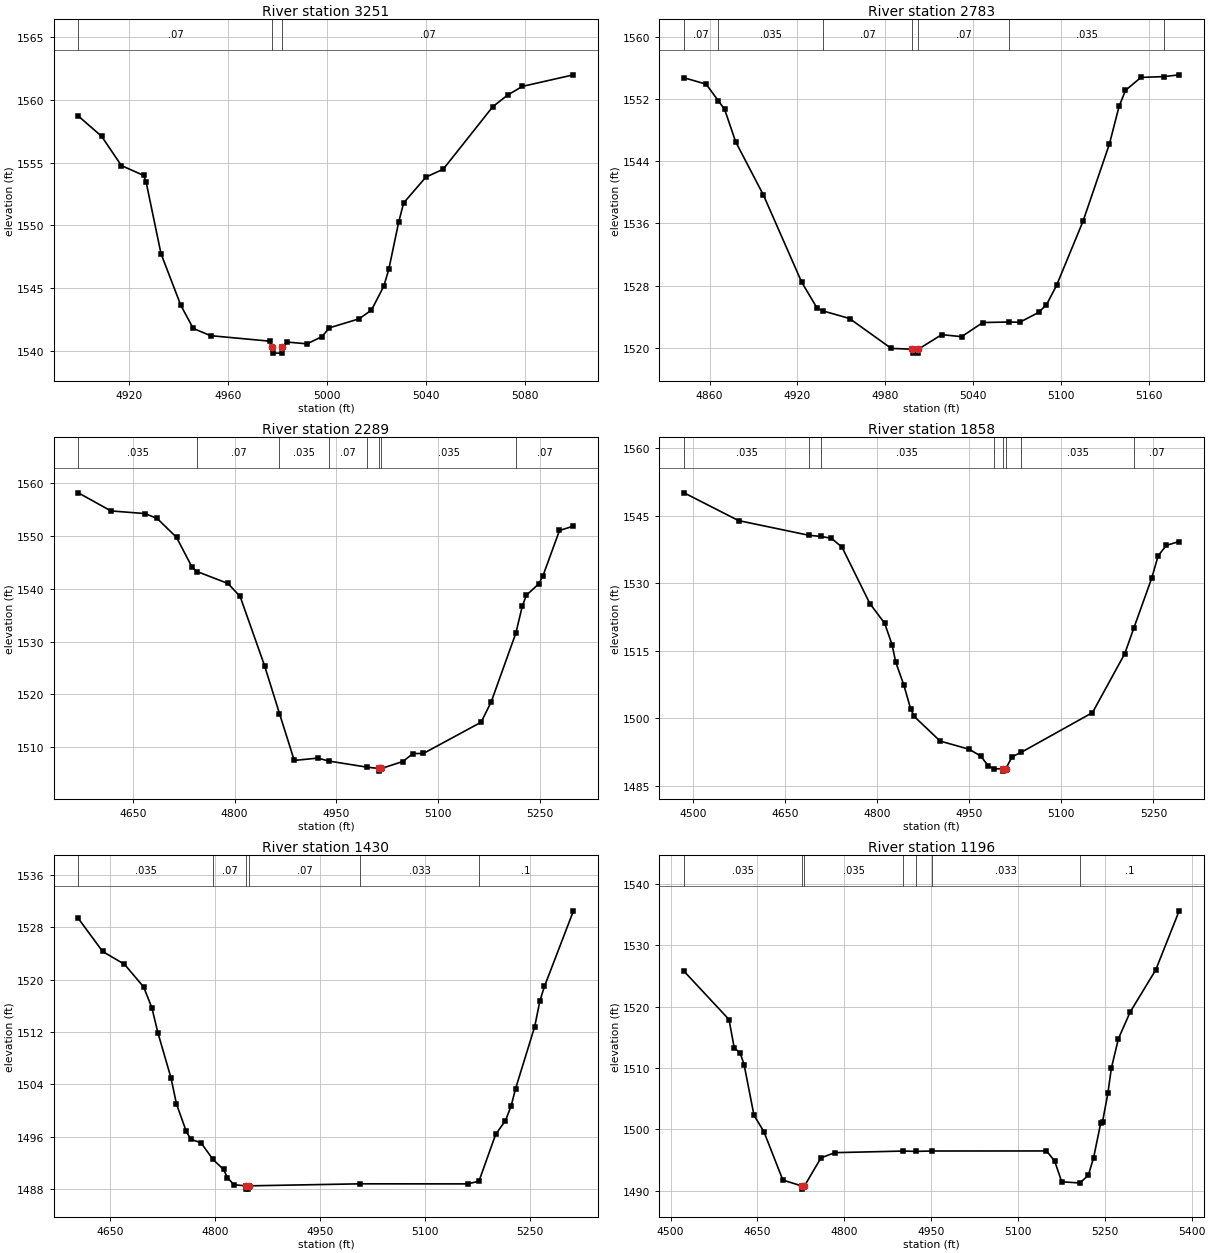
Type RM Length L Ch R = 1 ,3251    ,468,468,468
BEGIN DESCRIPTION:
Stream0028 7.0
END DESCRIPTION:
XS GIS Cut Line= 3
        1996025.       13888225.        1996125.       13888225.
        1996225.       13888225.
#Sta/Elev= 30
  4899.6 1558.71    4909  1557.1    4917 1554.77    4926 1553.98    4927 1553.45
    4933 1547.76    4941 1543.65    4946 1541.81    4953 1541.23    4977 1540.79
    4978 1540.34  4978.3 1539.84  4981.8 1539.84    4982 1540.34    4984 1540.72
    4992 1540.58    4998 1541.15    5001 1541.85    5013 1542.57    5018 1543.26
    5023 1545.17    5025  1546.5    5029 1550.26    5031 1551.79    5040 1553.85
    5047 1554.48    5067 1559.45    5073 1560.38    5079 1561.07  5099.6 1561.99
#Mann= 3 ,-1 , 0
  4899.6     .07       0    4978     .05       0    4982     .07       0
Bank Sta=4978,4982
XS Rating Curve= 0 ,0
Exp/Cntr=0.3,0.1

Type RM Length L Ch R = 1 ,2783    ,494,494,494
BEGIN DESCRIPTION:
Stream0028 6.0
END DESCRIPTION:
XS GIS Cut Line= 3
      1996025.01       13888625.        1996175.       13888675.
      1996325.02     13888574.99
#Sta/Elev= 30
  4842.5 1554.76  4857.6 1553.94    4866 1551.78  4870.2 1550.71  4877.8 1546.51
  4896.8 1539.64  4922.9 1528.43  4933.5 1525.07  4937.2 1524.74  4955.6 1523.75
  4984.1  1519.9  4998.6 1519.79  4998.9 1519.29  5002.4 1519.29  5002.6 1519.79
  5018.6 1521.67  5032.2 1521.41  5046.7 1523.23  5064.9  1523.3  5071.9 1523.26
  5084.8 1524.53  5090.2 1525.52  5097.1 1528.02  5115.2 1536.29  5133.2 1546.22
  5139.8 1551.06  5144.2 1553.14  5154.8 1554.81  5170.5 1554.91  5180.9 1555.14
#Mann= 7 ,-1 , 0
  4842.5     .07       0    4866    .035       0  4937.2     .07       0
  4998.6     .05       0  5002.6     .07       0  5064.9    .035       0
  5170.5     .07       0
Bank Sta=4998.6,5002.6
XS Rating Curve= 0 ,0
Exp/Cntr=0.3,0.1

Type RM Length L Ch R = 1 ,2289    ,431,431,431
BEGIN DESCRIPTION:
Stream0028 5.0
END DESCRIPTION:
XS GIS Cut Line= 3
      1996170.95     13889261.65        1996525.       13889025.
        1996575.       13888725.
#Sta/Elev= 30
  4569.7  1558.2  4617.8 1554.77  4667.5 1554.27  4685.6 1553.38  4714.5 1549.76
  4737.6 1544.05  4745.2 1543.25  4790.3 1541.01  4808.3 1538.54  4844.4 1525.37
  4866.3 1516.34  4888.1 1507.45  4922.8 1507.89    4939 1507.33    4995 1506.18
  5012.5 1505.92  5012.7 1505.42  5016.5 1505.92    5048 1507.24  5063.2 1508.75
  5078.4 1508.77  5163.5 1514.69  5178.5 1518.57  5214.7 1531.57  5224.4 1536.77
  5230.4 1538.79  5248.7 1540.96  5254.8 1542.48  5279.1 1551.06  5299.7 1551.89
#Mann= 8 ,-1 , 0
  4569.7    .035       0  4745.2     .07       0  4866.3    .035       0
    4939     .07       0    4995    .035       0  5012.5    .035       0
  5016.5    .035       0  5214.7     .07       0
Bank Sta=5012.5,5016.5
XS Rating Curve= 0 ,0
Exp/Cntr=0.3,0.1

Type RM Length L Ch R = 1 ,1858    ,428,428,428
BEGIN DESCRIPTION:
Stream0028 4.0
END DESCRIPTION:
XS GIS Cut Line= 3
      1996879.97     13889637.77        1996925.       13889125.
      1996774.99     13888874.99
#Sta/Elev= 30
  4485.7 1550.03  4574.5 1543.87  4689.5  1540.6  4708.2 1540.36  4725.7 1539.95
  4743.1 1537.94  4788.3 1525.46  4812.4 1521.09  4824.4 1516.36  4830.5 1512.43
  4843.6 1507.41  4854.6 1502.14  4860.6 1500.41  4902.7 1494.96  4950.2 1493.13
    4969 1491.63    4981 1489.45  4989.7 1488.82  5005.6 1488.79  5005.8 1488.29
  5009.6 1488.79  5019.9 1491.48  5034.8 1492.46  5150.8 1501.27  5203.3 1514.32
  5218.1 1520.01  5247.3 1531.11  5257.8 1536.08  5271.1 1538.37    5292 1539.23
#Mann= 8 ,-1 , 0
  4485.7    .035       0  4689.5     .07       0  4708.2    .035       0
  4989.7     .07       0  5005.6     .05       0  5009.6     .07       0
  5034.8    .035       0  5218.1     .07       0
Bank Sta=5005.6,5009.6
XS Rating Curve= 0 ,0
Exp/Cntr=0.3,0.1

Type RM Length L Ch R = 1 ,1430    ,234,234,234
BEGIN DESCRIPTION:
Stream0028 3.0
END DESCRIPTION:
XS GIS Cut Line= 3
      1997025.02     13889374.97        1997275.       13889075.
        1997375.       13888775.
#Sta/Elev= 30
  4604.8 1529.36  4639.5 1524.31  4670.7 1522.35  4698.1 1518.88  4709.8  1515.7
  4718.4 1511.89  4737.1 1504.98  4744.9 1501.01  4758.8 1496.84  4765.2 1495.63
  4780.1 1495.05  4796.9 1492.54  4812.1 1490.99  4817.7 1489.74  4826.9 1488.66
  4843.8 1488.49  4844.1 1487.99  4847.6 1487.99  4847.8 1488.49  5007.2  1488.8
  5160.3 1488.79  5176.6 1489.19  5200.5 1496.36  5214.5 1498.47  5222.6 1500.72
  5228.9 1503.35  5256.2 1512.83  5263.7 1516.81  5270.1 1518.96  5311.5 1530.52
#Mann= 6 ,-1 , 0
  4604.8    .035       0  4796.9     .07       0  4843.8     .05       0
  4847.8     .07       0  5007.2    .033       0  5176.6      .1       0
Bank Sta=4843.8,4847.8
XS Rating Curve= 0 ,0
Exp/Cntr=0.3,0.1

Type RM Length L Ch R = 1 ,1196    ,230,230,230
BEGIN DESCRIPTION:
Mapping XS 394f7b58
END DESCRIPTION:
XS GIS Cut Line= 3
      1997309.53     13889535.72       1997503.6     13889174.33
      1997412.94     13888738.66
#Sta/Elev= 30
  4523.3 1525.78    4601  1517.9    4610 1513.28  4620.2 1512.45    4627 1510.56
  4644.1 1502.29  4661.1 1499.63    4694 1491.71  4727.2 1490.73  4727.5 1490.23
  4731.2 1490.73  4759.8 1495.33  4783.7 1496.18  4900.9 1496.44  4923.8 1496.39
    4952 1496.45  5149.3 1496.46  5163.3 1494.84  5175.6 1491.43  5206.9 1491.23
  5221.6  1492.5  5230.7 1495.36    5243 1501.03  5246.1 1501.21  5255.3 1505.84
  5261.4    1510  5273.6 1514.79  5293.9 1519.14    5338    1526  5378.5 1535.64
#Mann= 7 ,-1 , 0
  4523.3    .035       0  4727.2    .033       0  4731.2    .035       0
  4900.9    .033       0  4923.8    .035       0    4952    .033       0
  5206.9      .1       0
Bank Sta=4727.2,4731.2
XS Rating Curve= 0 ,0
Exp/Cntr=0.3,0.1

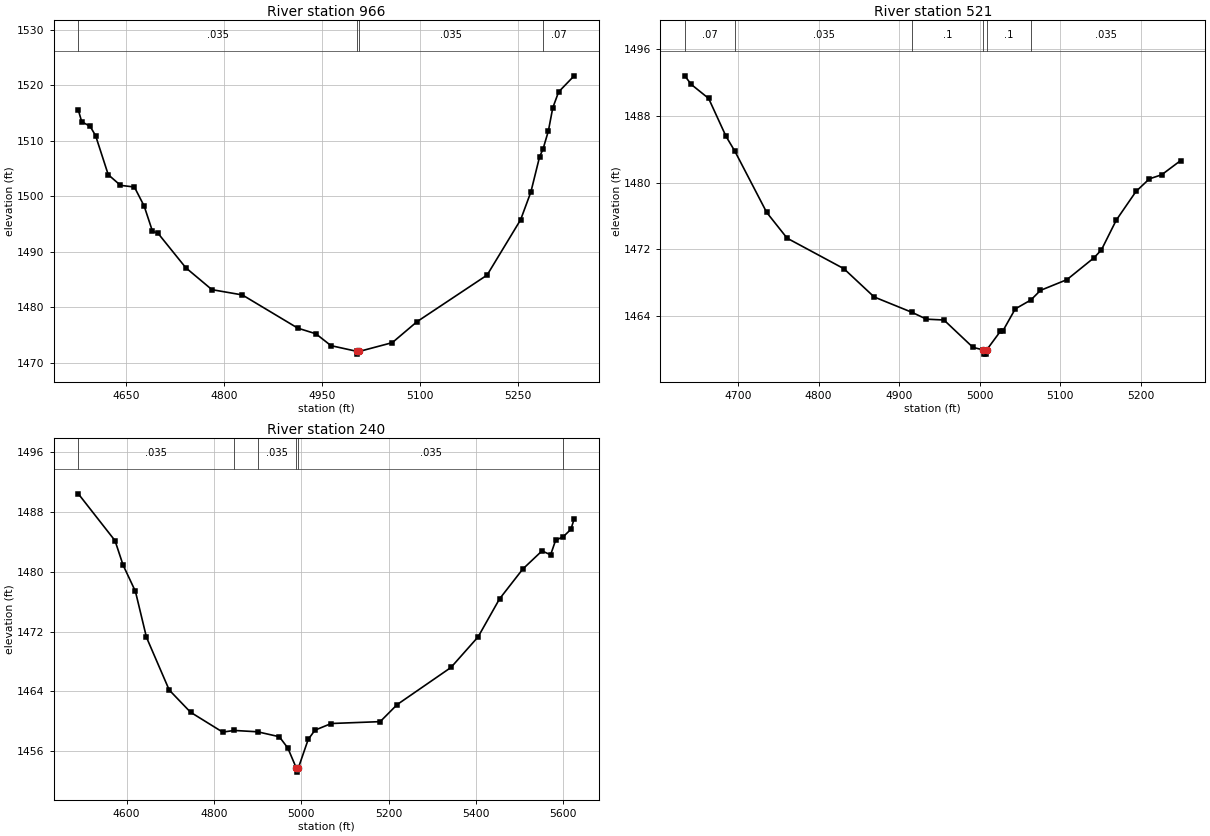
Type RM Length L Ch R = 1 ,966     ,445,445,445
BEGIN DESCRIPTION:
Stream0028 2.0
END DESCRIPTION:
XS GIS Cut Line= 3
      1997374.97     13889475.03        1997675.       13889175.
      1997824.99     13888875.02
#Sta/Elev= 30
  4576.3 1515.54  4581.5 1513.44  4594.3 1512.63  4602.8 1510.92  4622.1  1503.9
  4640.9 1501.97  4662.2 1501.67  4677.2 1498.22  4689.9 1493.69  4698.4 1493.32
  4740.9 1487.11    4781 1483.15  4827.6  1482.2  4912.5 1476.21  4940.3 1475.19
  4963.4 1473.05  5003.1 1472.02  5003.3 1471.52  5007.1 1472.02  5057.3 1473.59
  5095.3 1477.38  5202.6 1485.78    5254 1495.77  5269.7 1500.78  5283.1 1507.16
  5288.2 1508.47  5296.5 1511.79  5303.2 1515.94  5312.2 1518.83    5336 1521.73
#Mann= 4 ,-1 , 0
  4576.3    .035       0  5003.1    .035       0  5007.1    .035       0
  5288.2     .07       0
Bank Sta=5003.1,5007.1
XS Rating Curve= 0 ,0
Exp/Cntr=0.3,0.1

Type RM Length L Ch R = 1 ,521     ,281,281,281
BEGIN DESCRIPTION:
Stream0028 1.0
END DESCRIPTION:
XS GIS Cut Line= 3
      1997875.03     13889624.96        1998075.       13889325.
      1998024.99     13889074.96
#Sta/Elev= 30
  4633.8  1492.8  4641.8 1491.77  4663.4 1490.09    4685 1485.54  4696.1 1483.74
  4735.5 1476.42  4760.8 1473.34  4831.3 1469.68  4868.9 1466.29  4915.8 1464.45
  4933.8 1463.63  4955.5 1463.53  4991.5 1460.25  5004.5 1459.94  5004.8 1459.44
  5008.3 1459.44  5008.5 1459.94  5025.6 1462.18  5028.7 1462.23    5044 1464.86
  5063.4 1465.93  5075.3 1467.08  5108.2 1468.37  5141.9    1471    5151 1471.94
  5169.4  1475.5  5193.9 1478.94  5210.5 1480.45  5225.8 1480.94  5249.3 1482.64
#Mann= 6 ,-1 , 0
  4633.8     .07       0  4696.1    .035       0  4915.8      .1       0
  5004.5     .05       0  5008.5      .1       0  5063.4    .035       0
Bank Sta=5004.5,5008.5
XS Rating Curve= 0 ,0
Exp/Cntr=0.3,0.1

Type RM Length L Ch R = 1 ,240     ,0,0,0
BEGIN DESCRIPTION:
Stream0281 0.0
END DESCRIPTION:
XS GIS Cut Line= 4
      1998023.31     13889825.13       1998271.5     13889587.88
      1998337.62     13889349.81       1998192.7     13888824.66
#Sta/Elev= 30
  4489.4 1490.46  4573.4 1484.19  4591.8 1480.93  4620.1  1477.4  4645.4 1471.25
  4697.5 1464.19  4746.3 1461.22  4819.8 1458.56  4846.3 1458.78  4899.8  1458.6
  4949.5 1457.94    4969 1456.43  4988.8  1453.7    4989  1453.2  4992.8  1453.7
  5015.7 1457.58  5031.2 1458.82  5068.6 1459.71  5180.5 1459.96  5219.5 1462.25
  5342.5 1467.21  5404.7 1471.31  5453.7 1476.39    5507 1480.39    5551 1482.82
  5570.7 1482.29  5582.1 1484.24  5599.4 1484.71  5617.1  1485.7  5624.6  1487.1
#Mann= 6 ,-1 , 0
  4489.4    .035       0  4846.3      .1       0  4899.8    .035       0
  4988.8    .035       0  4992.8    .035       0  5599.4     .07       0
Bank Sta=4988.8,4992.8
XS Rating Curve= 0 ,0
Exp/Cntr=0.3,0.1

Chan Stop Cuts=-1
Use User Specified Reach Order=0
Composite Channel Slope=5