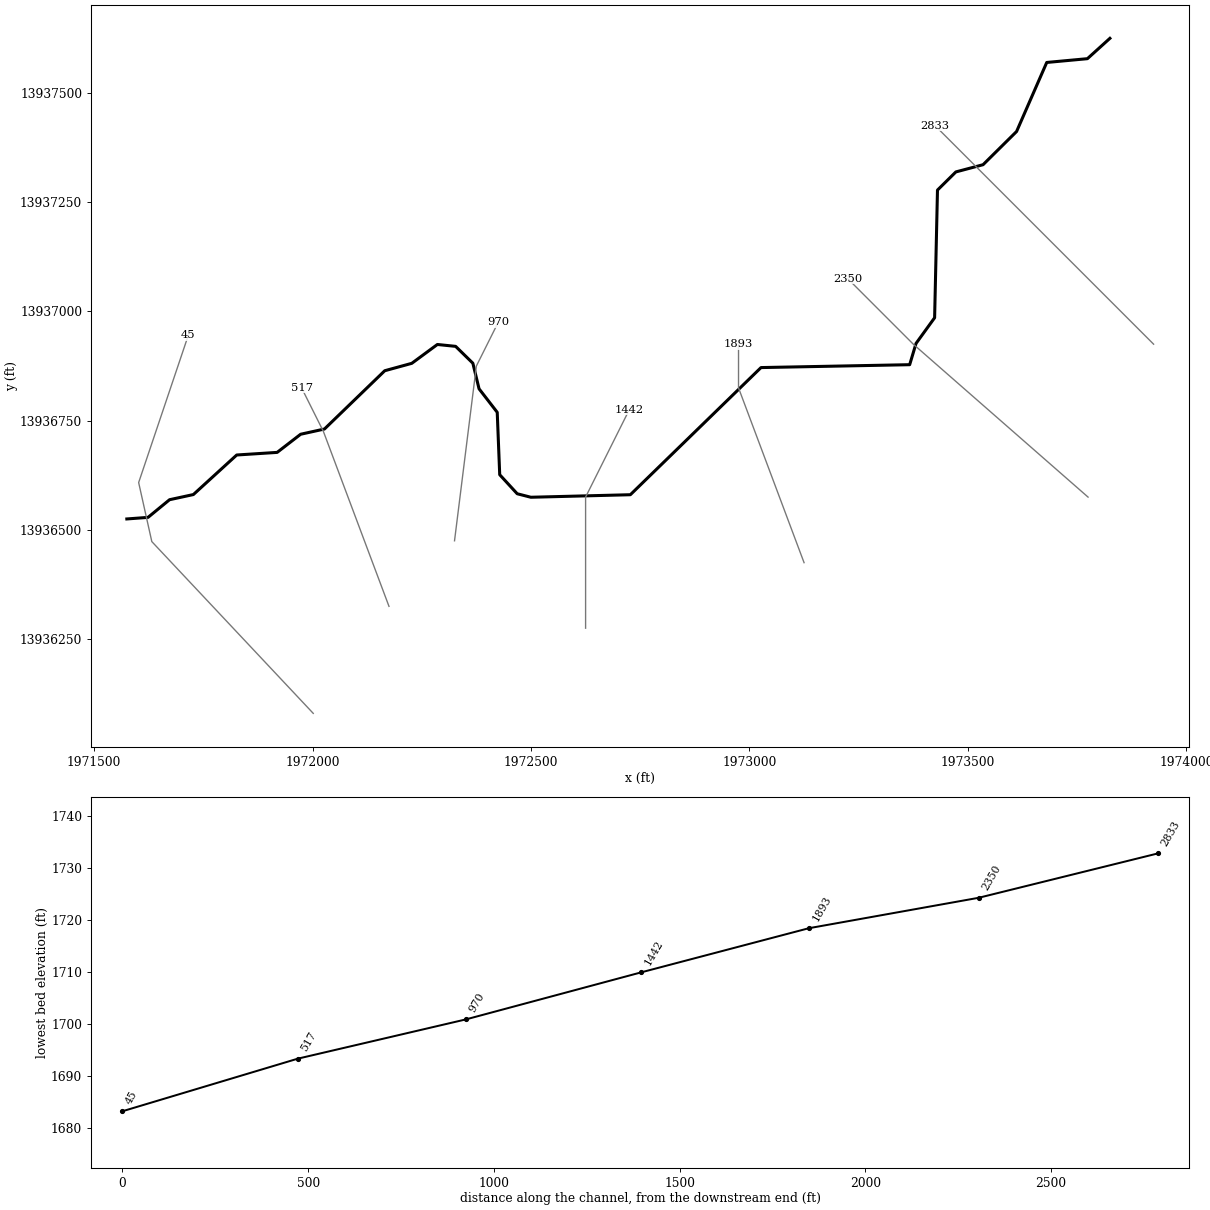
--- Stream0029.prj (project) ---

Proj Title=Stream0029 Base Level Engineering
Current Plan=p01
Default Exp/Contr=0.3,0.1
English Units
Geom File=g01
Flow File=f01
Plan File=p01
Y Axis Title=Elevation
X Axis Title(PF)=Main Channel Distance
X Axis Title(XS)=Station
BEGIN DESCRIPTION:
Stream0029
END DESCRIPTION:
DSS Export Rating Curves= 0
DSS Export Rating Curve Sorted= 0
DSS Export Volume Flow Curves= 0
DXF OffsetX= 0
DXF OffsetY= 0
DXF ScaleX= 1
DXF ScaleY= 10

--- Stream0029.p01 (plan) ---

Plan Title=Multiple Run
Short Identifier=Multiple
Geom File=g01
Flow File=f01
Subcritical Flow
K Sum by GR= 0
Std Step Tol= 0.01
Critical Tol= 0.01
Num of Std Step Trials= 20
Max Error Tol= 0.3
Flow Tol Ratio= 0.001
Split Flow NTrial= 30
Split Flow Tol= 0.02
Split Flow Ratio= 0.02
Log Output Level= 0
Friction Slope Method= 1
Unsteady Friction Slope Method= 2
Unsteady Bridges Friction Slope Method= 1
Parabolic Critical Depth
Global Vel Dist=  1 , 1 , 1
Global Log Level= 0
CheckData=True
Encroach Param= -1, 0, 0, 0
BEGIN DESCRIPTION:
Multiple Run
END DESCRIPTION:

--- Stream0029.f01 (steady flow) ---

Flow Title=Multiple
Number of Profiles=7
Profile Names=10-year,25-year,50-year,1pct_min,100-year,1pct_plu,500-year
River Rch & RM= Stream0029,Reach-1,2833
    1404    2455    3484    2396    4781    9540    8939
Boundary for River Rch & Prof#=Stream0029,Reach-1,1
Up Type=0
Dn Type=3
Dn Slope=0.005
Boundary for River Rch & Prof#=Stream0029,Reach-1,2
Up Type=0
Dn Type=3
Dn Slope=0.005
Boundary for River Rch & Prof#=Stream0029,Reach-1,3
Up Type=0
Dn Type=3
Dn Slope=0.005
Boundary for River Rch & Prof#=Stream0029,Reach-1,4
Up Type=0
Dn Type=3
Dn Slope=0.005
Boundary for River Rch & Prof#=Stream0029,Reach-1,5
Up Type=0
Dn Type=3
Dn Slope=0.005
Boundary for River Rch & Prof#=Stream0029,Reach-1,6
Up Type=0
Dn Type=3
Dn Slope=0.005
Boundary for River Rch & Prof#=Stream0029,Reach-1,7
Up Type=0
Dn Type=3
Dn Slope=0.005

--- Stream0029.g01 (geometry) ---

Geom Title=Existing Conditions
Program Version=4.10

River Reach=Stream0029      ,Reach-1
Reach XY= 30
        1973825.       13937625.       1973773.5     13937578.43
      1973680.42     13937569.79      1973611.39     13937411.76
      1973534.68     13937335.78      1973472.43     13937319.26
      1973430.36      13937277.7      1973423.81     13936985.48
      1973381.31     13936926.77      1973366.72     13936878.06
      1973026.46     13936871.46      1972727.45     13936580.46
      1972499.78     13936574.66      1972468.48     13936582.67
      1972428.44     13936626.22      1972422.75     13936769.07
      1972381.15     13936822.86      1972366.98     13936881.43
      1972327.55     13936920.02      1972285.75     13936924.32
      1972227.19     13936881.18      1972165.32     13936864.24
       1972027.3     13936730.83      1971972.83     13936718.86
      1971919.03     13936677.33       1971826.5     13936671.38
       1971727.3     13936580.83      1971672.76     13936569.03
      1971623.51      13936528.6        1971575.       13936525.

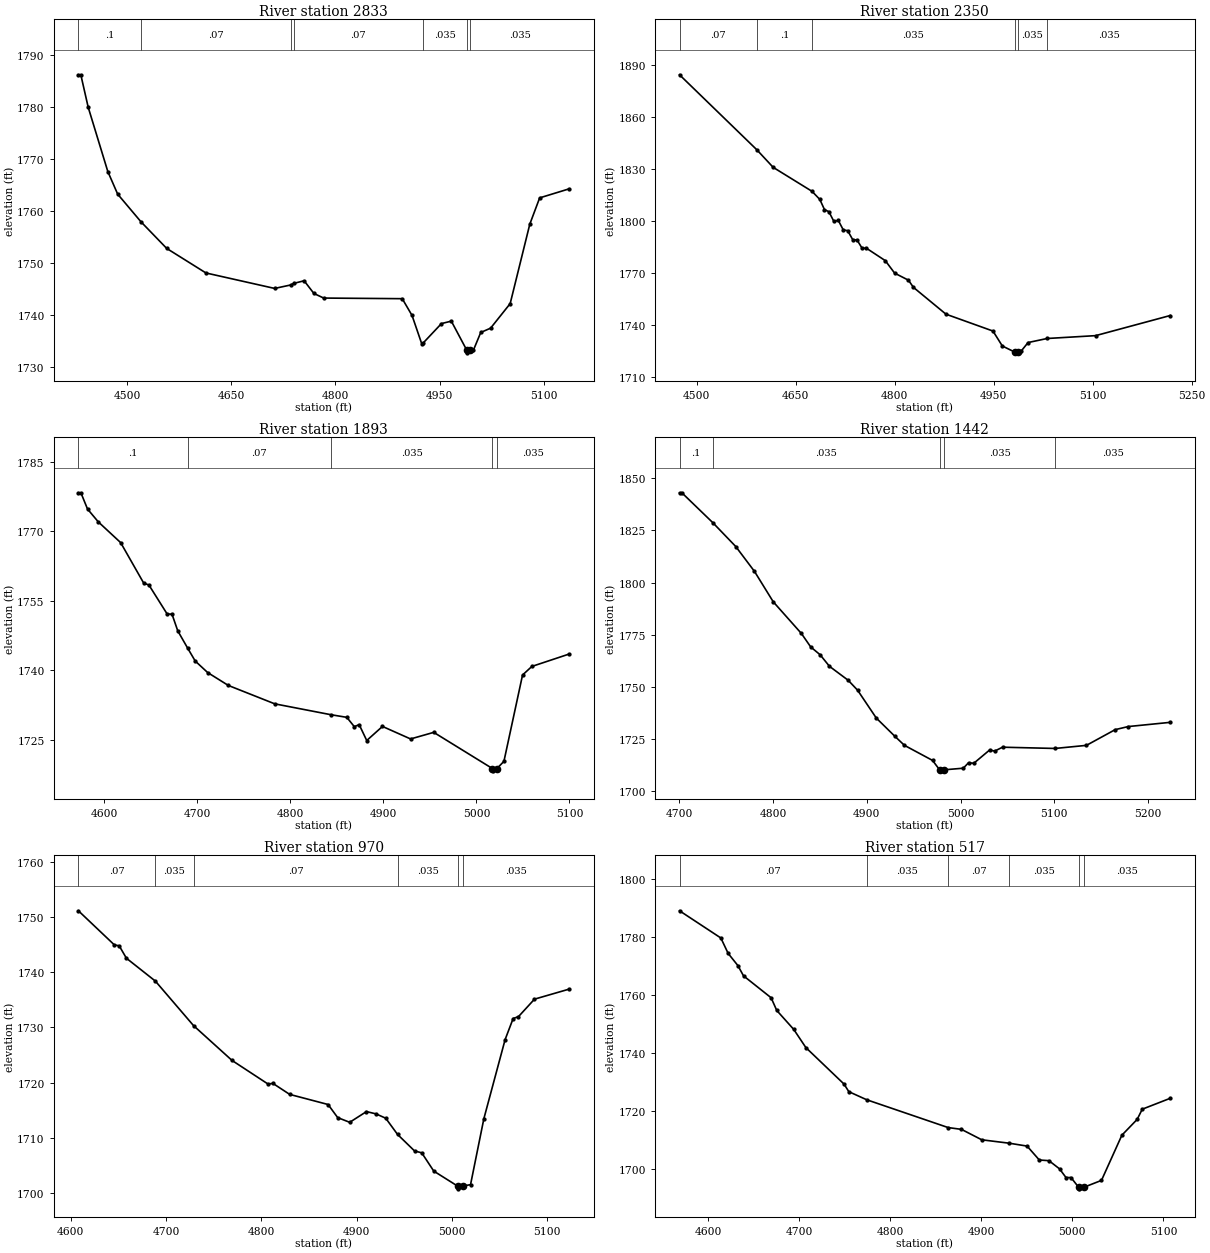
Type RM Length L Ch R = 1 ,2833    ,483,483,483
BEGIN DESCRIPTION:
Stream0029 6.0
END DESCRIPTION:
XS GIS Cut Line= 3
      1973924.99     13936925.01        1973525.       13937325.
      1973424.99     13937425.01
#Sta/Elev= 30
  4429.5 1786.13    4433 1786.13  4443.6 1779.91  4471.9 1767.55  4486.1 1763.21
  4519.8 1757.88  4556.8 1752.78  4613.3 1748.07  4712.3  1745.1  4735.3 1745.76
  4739.9 1746.07  4754.8 1746.57  4768.9 1744.13    4783 1743.25  4896.2 1743.13
  4910.3 1739.91  4924.5 1734.38  4926.2  1734.6  4952.7 1738.35  4966.9 1738.82
  4989.2 1733.23  4989.6 1732.73    4994 1733.23  4998.7 1733.23  5009.3 1736.64
  5023.5 1737.47  5051.7 1742.18    5080 1757.44  5094.2 1762.49  5136.6 1764.22
#Mann= 7 ,-1 , 0
  4429.5      .1       0  4519.8     .07       0  4735.3      .1       0
  4739.9     .07       0  4926.2    .035       0  4989.2    .035       0
    4994    .035       0
Bank Sta=4989.2,4994
XS Rating Curve= 0 ,0
Exp/Cntr=0.3,0.1

Type RM Length L Ch R = 1 ,2350    ,457,457,457
BEGIN DESCRIPTION:
Stream0029 5.0
END DESCRIPTION:
XS GIS Cut Line= 3
      1973774.98     13936575.02        1973375.       13936925.
      1973225.01     13937074.99
#Sta/Elev= 30
  4473.8 1884.63  4590.9 1841.38  4615.7 1831.22  4674.6 1817.38  4686.4 1812.71
  4693.5 1806.81  4700.1 1805.65  4707.7 1800.03  4714.4  1800.6    4722 1795.09
  4728.6 1794.69  4736.2 1789.55  4742.9 1789.24  4750.4 1784.59  4757.1 1784.53
  4785.6 1777.39  4799.8 1770.18  4820.7 1766.11  4828.3 1761.96  4877.6 1746.49
  4948.8 1736.76    4963 1728.14  4981.5 1724.69  4981.9 1724.19  4986.3 1724.69
  4991.5 1725.19    5002 1730.13  5030.9 1732.47  5104.3 1734.11  5217.4 1745.72
#Mann= 6 ,-1 , 0
  4473.8     .07       0  4590.9      .1       0  4674.6    .035       0
  4981.5    .035       0  4986.3    .035       0  5030.9    .035       0
Bank Sta=4981.5,4986.3
XS Rating Curve= 0 ,0
Exp/Cntr=0.3,0.1

Type RM Length L Ch R = 1 ,1893    ,451,451,451
BEGIN DESCRIPTION:
Stream0029 4.0
END DESCRIPTION:
XS GIS Cut Line= 3
      1973125.01     13936424.96        1972975.       13936825.
        1972975.     13936924.96
#Sta/Elev= 30
  4572.4 1778.32  4575.1 1778.32  4582.2 1774.82  4593.8 1772.04  4617.8 1767.57
  4642.7 1758.79  4648.1 1758.45  4667.7 1752.19    4673 1752.12  4679.2 1748.52
  4689.7 1744.84  4697.9 1742.03  4711.3 1739.54  4733.5 1736.76  4783.4 1732.79
  4843.9 1730.44  4860.8 1729.88  4868.8 1727.88  4874.1  1728.3  4882.2 1724.88
  4899.1 1727.92  4929.3 1725.22  4954.2 1726.64  5017.2 1718.84  5017.5 1718.34
  5022.1 1718.84  5029.6 1720.39  5049.6 1739.01  5059.6 1740.86  5099.6 1743.53
#Mann= 5 ,-1 , 0
  4572.4      .1       0  4689.7     .07       0  4843.9    .035       0
  5017.2    .035       0  5022.1    .035       0
Bank Sta=5017.2,5022.1
XS Rating Curve= 0 ,0
Exp/Cntr=0.3,0.1

Type RM Length L Ch R = 1 ,1442    ,472,472,472
BEGIN DESCRIPTION:
Stream0029 3.0
END DESCRIPTION:
XS GIS Cut Line= 3
        1972625.     13936274.99        1972625.       13936575.
      1972724.99     13936774.99
#Sta/Elev= 30
  4700.1 1843.01  4702.6 1843.01  4735.7 1828.66  4760.1 1817.28  4780.1 1805.35
  4800.1 1790.81  4830.1 1775.66  4840.1 1769.18  4850.1 1765.46  4860.1 1759.91
  4880.1 1753.22  4890.1 1748.48  4910.1 1735.12  4930.1 1726.31  4940.1 1722.07
  4970.1 1714.85  4977.6 1710.36    4978 1709.86  4982.6 1710.36  5002.9 1711.12
  5008.5 1713.74  5014.1 1713.48  5030.9  1719.8  5036.4 1719.33  5044.8 1721.18
  5100.8 1720.58  5134.3 1722.06    5165 1729.59    5179 1731.07  5223.7 1733.08
#Mann= 5 ,-1 , 0
  4700.1      .1       0  4735.7    .035       0  4977.6    .035       0
  4982.6    .035       0  5100.8    .035       0
Bank Sta=4977.6,4982.6
XS Rating Curve= 0 ,0
Exp/Cntr=0.3,0.1

Type RM Length L Ch R = 1 ,970     ,453,453,453
BEGIN DESCRIPTION:
Stream0029 2.0
END DESCRIPTION:
XS GIS Cut Line= 3
        1972325.       13936475.        1972375.       13936875.
      1972424.99     13936974.99
#Sta/Elev= 30
  4607.9 1751.09  4645.7 1744.91  4650.7 1744.76  4658.3 1742.51  4688.7 1738.37
  4728.7 1730.33  4769.1 1724.03  4806.9 1719.76    4812 1719.88  4829.6 1717.89
  4869.9 1716.06    4880 1713.69  4892.6 1712.84  4910.2 1714.78  4920.3 1714.36
  4930.4 1713.58  4942.8 1710.65  4960.6 1707.67  4968.2 1707.32  4980.8 1704.02
  5005.8 1701.31  5006.3 1700.81  5011.1 1701.31  5019.4 1701.57  5033.4 1713.51
  5055.7 1727.81  5064.1 1731.61  5069.7 1731.95  5086.5 1735.11  5122.8 1736.92
#Mann= 6 ,-1 , 0
  4607.9     .07       0  4688.7    .035       0  4728.7     .07       0
  4942.8    .035       0  5005.8    .035       0  5011.1    .035       0
Bank Sta=5005.8,5011.1
XS Rating Curve= 0 ,0
Exp/Cntr=0.3,0.1

Type RM Length L Ch R = 1 ,517     ,472,472,472
BEGIN DESCRIPTION:
Stream0029 1.0
END DESCRIPTION:
XS GIS Cut Line= 3
        1972175.       13936325.        1972025.       13936725.
        1971975.       13936825.
#Sta/Elev= 30
  4568.5 1789.01  4613.9 1779.64  4621.9 1774.34  4632.6 1770.14  4638.8  1766.6
  4669.1 1759.06  4675.3 1754.69    4694 1748.14  4707.3 1741.89  4749.2 1729.33
  4754.5 1726.71  4774.1 1723.93  4863.6 1714.35  4878.2 1713.73  4900.5 1710.14
  4930.8 1708.96  4950.3 1707.97  4963.7 1703.18  4974.3 1702.95  4985.9 1700.14
    4993 1697.15  4998.5 1697.15    5007 1693.75  5007.4 1693.25  5012.3 1693.75
    5032 1696.16  5054.4 1711.72  5071.2 1717.17  5076.8 1720.68  5107.5 1724.43
#Mann= 6 ,-1 , 0
  4568.5     .07       0  4774.1    .035       0  4863.6     .07       0
  4930.8    .035       0    5007    .035       0  5012.3    .035       0
Bank Sta=5007,5012.3
XS Rating Curve= 0 ,0
Exp/Cntr=0.3,0.1

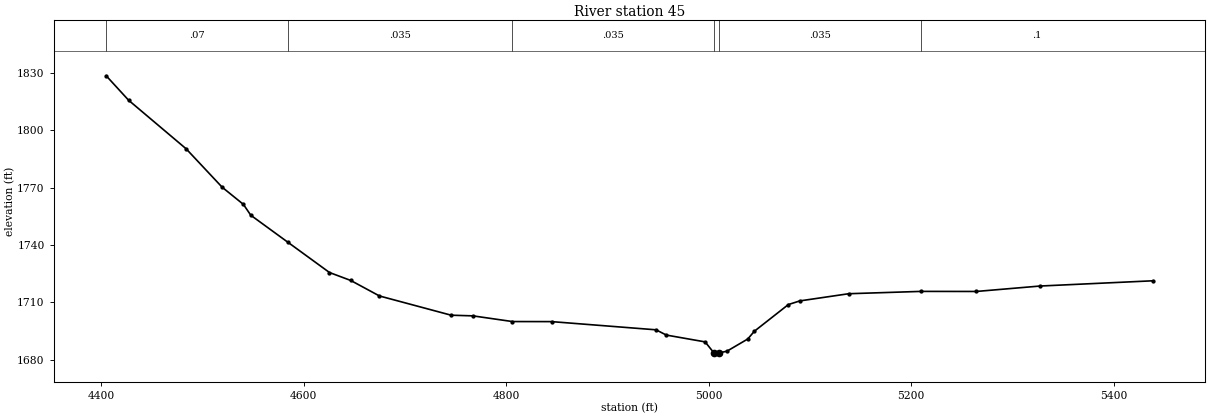
Type RM Length L Ch R = 1 ,45      ,0,0,0
BEGIN DESCRIPTION:
Stream0029 0.0
END DESCRIPTION:
XS GIS Cut Line= 4
      1972001.67     13936080.02      1971632.19     13936473.19
      1971602.07     13936608.29       1971715.8     13936945.58
#Sta/Elev= 30
  4404.9 1828.61  4427.1 1815.78  4483.8 1790.43  4519.4 1770.32  4540.4 1761.33
  4547.7 1755.65  4584.2 1741.57  4625.4 1725.69  4646.4 1721.53  4674.8 1713.41
  4745.6 1703.35    4767 1703.01  4806.1 1700.03  4844.7    1700  4947.9 1695.71
  4958.1 1692.96  4996.4 1689.39  5005.1 1683.64  5005.5 1683.14  5010.4 1683.64
    5018 1684.54  5038.5  1690.9    5045 1694.95  5078.6 1708.92  5089.9 1710.83
  5138.2 1714.59  5209.8 1715.81  5264.1 1715.77  5327.1 1718.61  5438.8 1721.36
#Mann= 6 ,-1 , 0
  4404.9     .07       0  4584.2    .035       0  4806.1    .035       0
  5005.1    .035       0  5010.4    .035       0  5209.8      .1       0
Bank Sta=5005.1,5010.4
XS Rating Curve= 0 ,0
Exp/Cntr=0.3,0.1

Chan Stop Cuts=-1
Use User Specified Reach Order=0
Composite Channel Slope=5