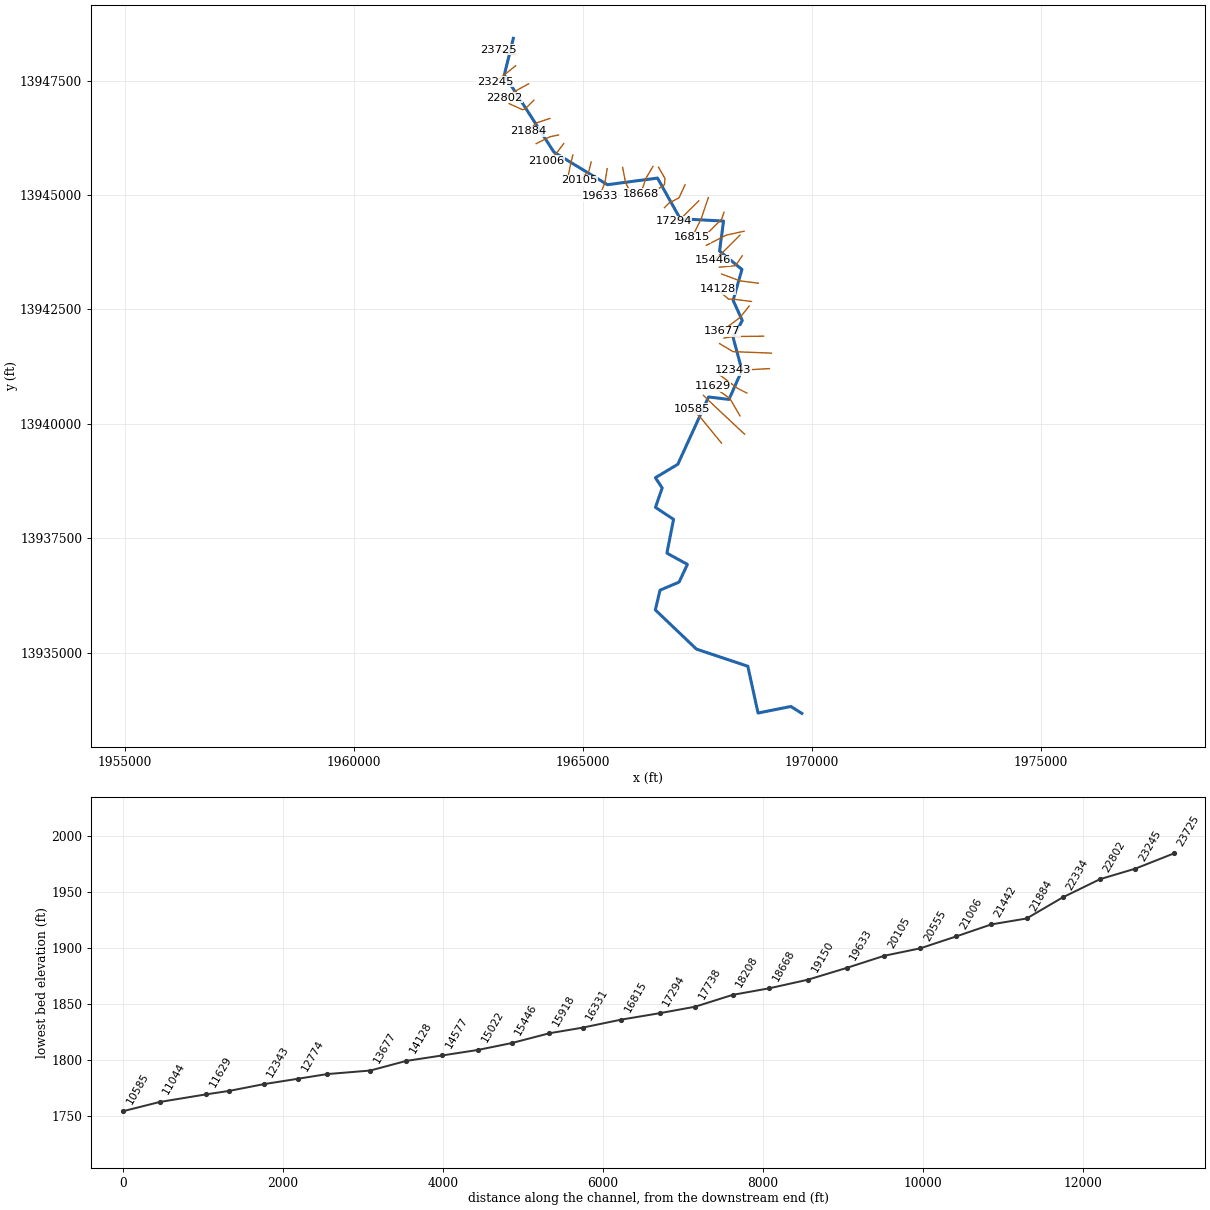
--- Stream0030.prj (project) ---

Proj Title=Stream0030 Base Level Engineering
Current Plan=p01
Default Exp/Contr=0.3,0.1
English Units
Geom File=g01
Flow File=f01
Plan File=p01
BEGIN DESCRIPTION:
Stream0030
END DESCRIPTION:

--- Stream0030.p01 (plan) ---

Plan Title=Multiple Run
Short Identifier=Multiple
Geom File=g01
Flow File=f01
Subcritical Flow
K Sum by GR= 0
Std Step Tol= 0.01
Critical Tol= 0.01
Num of Std Step Trials= 20
Max Error Tol= 0.3
Flow Tol Ratio= 0.001
Split Flow NTrial= 30
Split Flow Tol= 0.02
Split Flow Ratio= 0.02
Log Output Level= 0
Friction Slope Method= 1
Unsteady Friction Slope Method= 2
Unsteady Bridges Friction Slope Method= 1
Parabolic Critical Depth
Global Vel Dist=  1 , 1 , 1
Global Log Level= 0
CheckData=True
Encroach Param= -1, 0, 0, 0
BEGIN DESCRIPTION:
Multiple Run
END DESCRIPTION:

--- Stream0030.f01 (steady flow) ---

Flow Title=Multiple
Number of Profiles=7
Profile Names=10-year,25-year,50-year,1pct_min,100-year,1pct_plu,500-year
River Rch & RM= Stream0030,Reach-1,23725
     344     544     720     465     927    1849    1507
River Rch & RM= Stream0030,Reach-1,23245
     641    1059    1446     959    1913    3817    3296
River Rch & RM= Stream0030,Reach-1,21884
    1206    2071    2903    1968    3926    7834    7089
River Rch & RM= Stream0030,Reach-1,20105
    1549    2698    3816    2608    5203   10381    9551
River Rch & RM= Stream0030,Reach-1,17738
    2097    3681    5231    3587    7156   14279   13228
River Rch & RM= Stream0030,Reach-1,8955
    2311    4076    5811    3996    7973   15907   14825
River Rch & RM= Stream0030,Reach-1,8119
    2914    5197    7463    5164   10303   20558   19409
River Rch & RM= Stream0030,Reach-1,4303
    3044    5436    7815    5413   10800   21549   20383
River Rch & RM= Stream0030,Reach-1,2875
    3263    5844    8416    5837   11647   23238   22045
Boundary for River Rch & Prof#=Stream0030,Reach-1,1
Up Type=0
Dn Type=3
Dn Slope=0.005
Boundary for River Rch & Prof#=Stream0030,Reach-1,2
Up Type=0
Dn Type=3
Dn Slope=0.005
Boundary for River Rch & Prof#=Stream0030,Reach-1,3
Up Type=0
Dn Type=3
Dn Slope=0.005
Boundary for River Rch & Prof#=Stream0030,Reach-1,4
Up Type=0
Dn Type=3
Dn Slope=0.005
Boundary for River Rch & Prof#=Stream0030,Reach-1,5
Up Type=0
Dn Type=3
Dn Slope=0.005
Boundary for River Rch & Prof#=Stream0030,Reach-1,6
Up Type=0
Dn Type=3
Dn Slope=0.005
Boundary for River Rch & Prof#=Stream0030,Reach-1,7
Up Type=0
Dn Type=3
Dn Slope=0.005

--- Stream0030.g01 (geometry) ---

Geom Title=Existing Conditions

River Reach=Stream0030,Reach-1
Reach XY= 30
      1963475.00     13948425.00      1963278.53     13947626.47
      1964361.65     13945938.36      1965530.94     13945227.26
      1966623.54     13945371.46      1967118.94     13944483.14
      1968065.86     13944431.75      1967978.12     13943776.63
      1968467.47     13943375.01      1968274.60     13942700.00
      1968474.62     13942259.84      1968274.48     13941890.26
      1968466.92     13941171.70      1968184.70     13940535.18
      1967738.44     13940588.64      1967067.18     13939118.81
      1966577.99     13938823.60      1966725.59     13938600.00
      1966578.74     13938176.55      1966973.92     13937914.46
      1966828.53     13937176.45      1967276.01     13936930.43
      1967095.54     13936544.47      1966678.50     13936366.54
      1966576.12     13935935.46      1967472.50     13935080.35
      1968595.39     13934705.16      1968818.79     13933682.80
      1969535.05     13933825.78      1969775.00     13933675.00

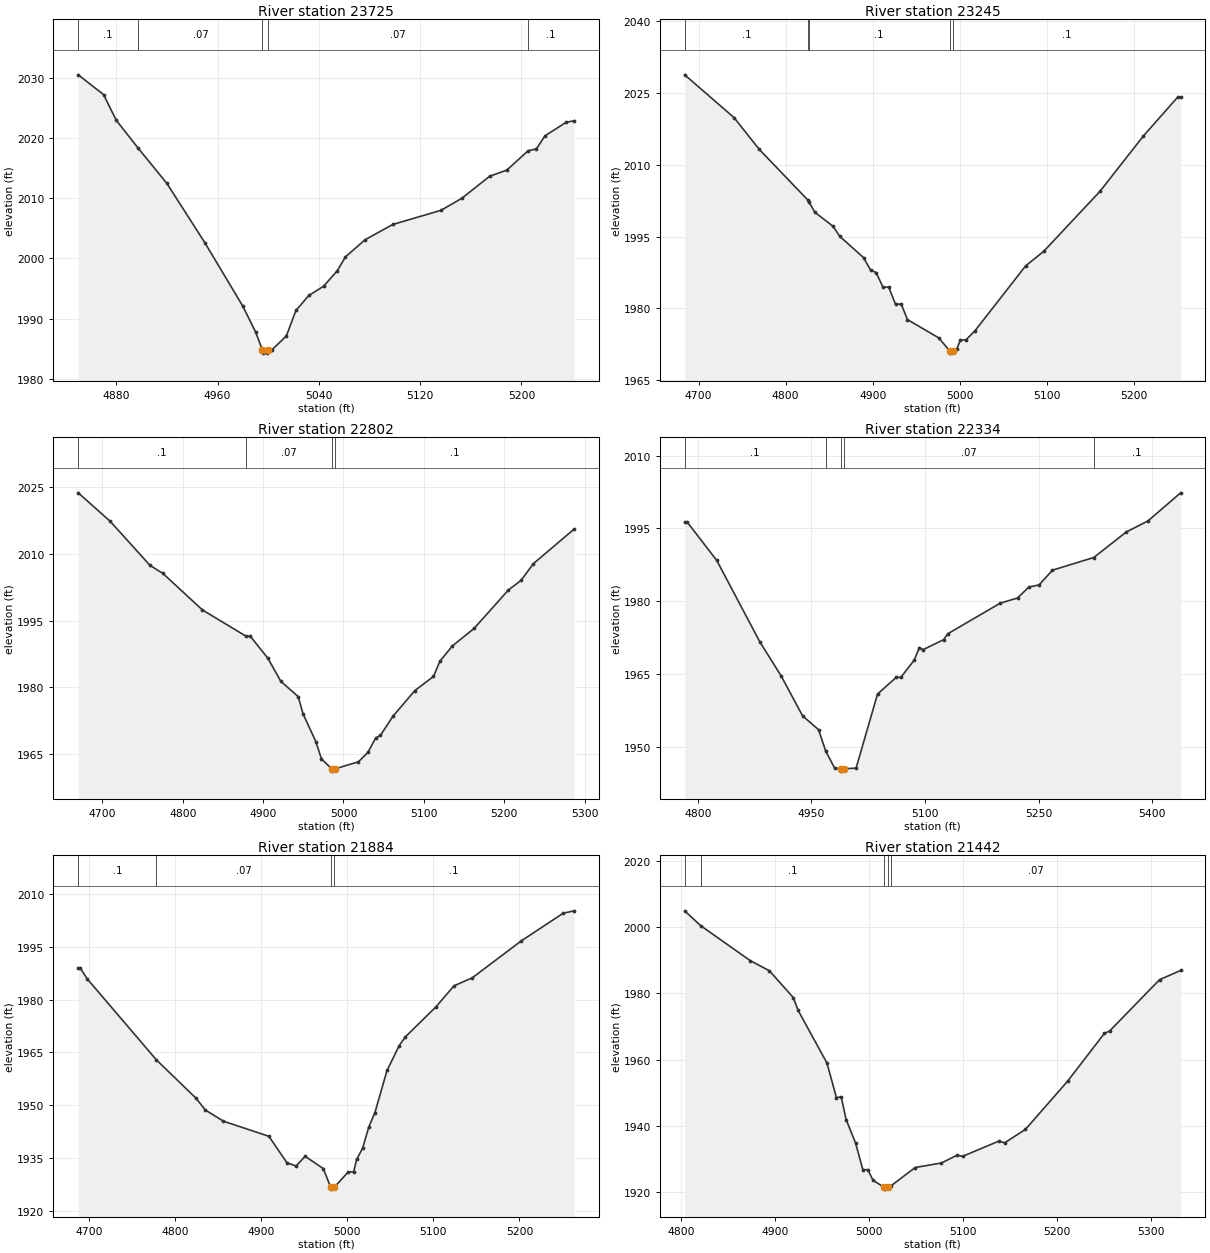
Type RM Length L Ch R = 1,23725,480,480,480
BEGIN DESCRIPTION:
Stream0030 52.0
END DESCRIPTION:
XS GIS Cut Line= 3
      1963524.99     13948075.00      1963375.00     13948075.00
      1963153.97     13948172.56
#Sta/Elev= 30
  4850.0 2030.59  4870.0 2027.30  4880.0 2023.03  4897.4 2018.36  4920.0 2012.51
  4950.0 2002.63  4980.0 1992.05  4990.0 1987.79  4995.5 1984.74  4995.7 1984.24
  4999.2 1984.24  4999.5 1984.74  5002.7 1984.74  5014.4 1987.11  5021.9 1991.35
  5032.2 1993.86  5043.7 1995.37  5054.6 1997.97  5061.0 2000.27  5076.5 2003.12
  5098.4 2005.67  5136.4 2008.02  5153.0 2010.04  5174.9 2013.70  5188.5 2014.73
  5205.2 2017.94  5211.8 2018.26  5218.6 2020.44  5235.1 2022.66  5241.6 2022.95
#Mann=5,-1,0
  4850.0     0.1       0  4897.4    0.07       0  4995.5    0.05       0
  4999.5    0.07       0  5205.2     0.1       0
Bank Sta=4995.5,4999.5
Exp/Cntr=0.3,0.1

Type RM Length L Ch R = 1,23245,443,443,443
BEGIN DESCRIPTION:
Stream0030 51.0
END DESCRIPTION:
XS GIS Cut Line= 3
      1963525.00     13947825.00      1963275.00     13947625.00
      1963074.97     13947474.97
#Sta/Elev= 30
  4683.9 2028.84  4740.7 2019.89  4769.5 2013.29  4825.7 2002.63  4826.6 2002.34
  4833.6 2000.10  4854.4 1997.19  4862.4 1995.05  4889.6 1990.62  4897.6 1988.03
  4904.0 1987.52  4912.0 1984.43  4918.4 1984.49  4926.4 1980.85  4932.8 1980.95
  4940.0 1977.69  4976.0 1973.85  4988.5 1971.17  4988.7 1970.67  4992.5 1971.17
  4996.9 1971.57  5000.9 1973.43  5007.2 1973.43  5017.6 1975.32  5075.9 1988.91
  5096.8 1991.96  5161.3 2004.47  5211.3 2016.06  5250.9 2024.21  5254.1 2024.21
#Mann=5,-1,0
  4683.9     0.1       0  4825.7    0.07       0  4826.6     0.1       0
  4988.5    0.05       0  4992.5     0.1       0
Bank Sta=4988.5,4992.5
Exp/Cntr=0.3,0.1

Type RM Length L Ch R = 1,22802,468,468,468
BEGIN DESCRIPTION:
Stream0030 50.0
END DESCRIPTION:
XS GIS Cut Line= 3
      1963809.89     13947432.25      1963525.00     13947275.00
      1963274.96     13947124.97
#Sta/Elev= 30
  4670.0 2023.63  4709.8 2017.25  4759.3 2007.37  4775.4 2005.55  4824.6 1997.37
  4878.4 1991.54  4884.2 1991.46  4906.0 1986.54  4922.1 1981.37  4943.7 1977.95
  4949.7 1974.11  4965.6 1967.87  4972.6 1964.01  4985.4 1961.75  4985.6 1961.25
  4989.4 1961.75  5018.7 1963.35  5030.4 1965.45  5040.1 1968.68  5045.9 1969.24
  5061.5 1973.53  5088.7 1979.29  5112.0 1982.47  5119.8 1985.83  5135.3 1989.28
  5162.6 1993.25  5205.3 2001.86  5220.9 2004.00  5236.4 2007.77  5287.0 2015.51
#Mann=4,-1,0
  4670.0     0.1       0  4878.4    0.07       0  4985.4    0.05       0
  4989.4     0.1       0
Bank Sta=4985.4,4989.4
Exp/Cntr=0.3,0.1

Type RM Length L Ch R = 1,22334,450,450,450
BEGIN DESCRIPTION:
Stream0030 49.0
END DESCRIPTION:
XS GIS Cut Line= 5
      1963925.01     13947075.01      1963775.00     13946925.00
      1963725.00     13946875.00      1963673.87     13946865.88
      1963382.81     13946998.87
#Sta/Elev= 30
  4782.8 1996.24  4786.4 1996.24  4825.2 1988.38  4881.8 1971.66  4910.1 1964.58
  4938.4 1956.35  4959.6 1953.47  4968.9 1949.10  4980.8 1945.55  4989.4 1945.43
  4989.7 1944.93  4993.4 1945.43  5009.1 1945.54  5037.4 1960.82  5062.1 1964.27
  5068.2 1964.27  5086.0 1967.85  5092.6 1970.41  5097.7 1969.99  5124.7 1972.04
  5130.2 1973.26  5199.3 1979.56  5222.3 1980.64  5237.3 1982.90  5250.8 1983.34
  5268.3 1986.37  5322.9 1988.99  5365.9 1994.26  5394.5 1996.53  5437.6 2002.33
#Mann=5,-1,0
  4782.8     0.1       0  4968.9    0.07       0  4989.4    0.05       0
  4993.4    0.07       0  5322.9     0.1       0
Bank Sta=4989.4,4993.4
Exp/Cntr=0.3,0.1

Type RM Length L Ch R = 1,21884,442,442,442
BEGIN DESCRIPTION:
Stream0030 48.0
END DESCRIPTION:
XS GIS Cut Line= 3
      1964275.00     13946675.00      1963975.00     13946575.00
      1963791.01     13946391.76
#Sta/Elev= 30
  4687.7 1988.95  4690.3 1988.95  4698.2 1985.93  4778.6 1962.87  4824.7 1951.95
  4835.3 1948.64  4856.4 1945.45  4909.1 1941.16  4930.1 1933.62  4940.7 1932.72
  4951.2 1935.46  4972.3 1931.98  4980.9 1926.63  4981.1 1926.13  4984.9 1926.63
  5001.3 1931.02  5007.5 1931.02  5011.0 1934.56  5018.1 1937.85  5025.1 1943.79
  5032.2 1947.85  5046.3 1959.88  5060.5 1966.98  5067.6 1969.44  5102.9 1977.93
  5124.1 1983.97  5145.3 1986.24  5201.9 1996.69  5250.9 2004.63  5263.6 2005.30
#Mann=4,-1,0
  4687.7     0.1       0  4778.6    0.07       0  4980.9    0.05       0
  4984.9     0.1       0
Bank Sta=4980.9,4984.9
Exp/Cntr=0.3,0.1

Type RM Length L Ch R = 1,21442,436,436,436
BEGIN DESCRIPTION:
Stream0030 47.0
END DESCRIPTION:
XS GIS Cut Line= 3
      1964463.33     13946312.61      1964275.00     13946275.00
      1963974.96     13946124.98
#Sta/Elev= 30
  4804.1 2004.98  4821.1 2000.50  4873.8 1989.92  4894.2 1986.86  4919.6 1978.75
  4924.8 1974.85  4955.4 1958.97  4965.5 1948.50  4970.6 1948.74  4975.8 1941.86
  4985.9 1934.75  4993.6 1926.70  4998.9 1926.70  5004.5 1923.47  5016.5 1921.32
  5016.8 1920.82  5020.5 1921.32  5023.1 1921.72  5049.3 1927.36  5077.2 1928.73
  5094.0 1931.09  5099.6 1930.72  5138.7 1935.39  5144.3 1934.79  5166.6 1938.90
  5211.4 1953.47  5250.5 1967.91  5256.1 1968.64  5309.2 1984.16  5331.6 1986.94
#Mann=5,-1,0
  4804.1    0.07       0  4821.1     0.1       0  5016.5    0.05       0
  5020.5     0.1       0  5023.1    0.07       0
Bank Sta=5016.5,5020.5
Exp/Cntr=0.3,0.1

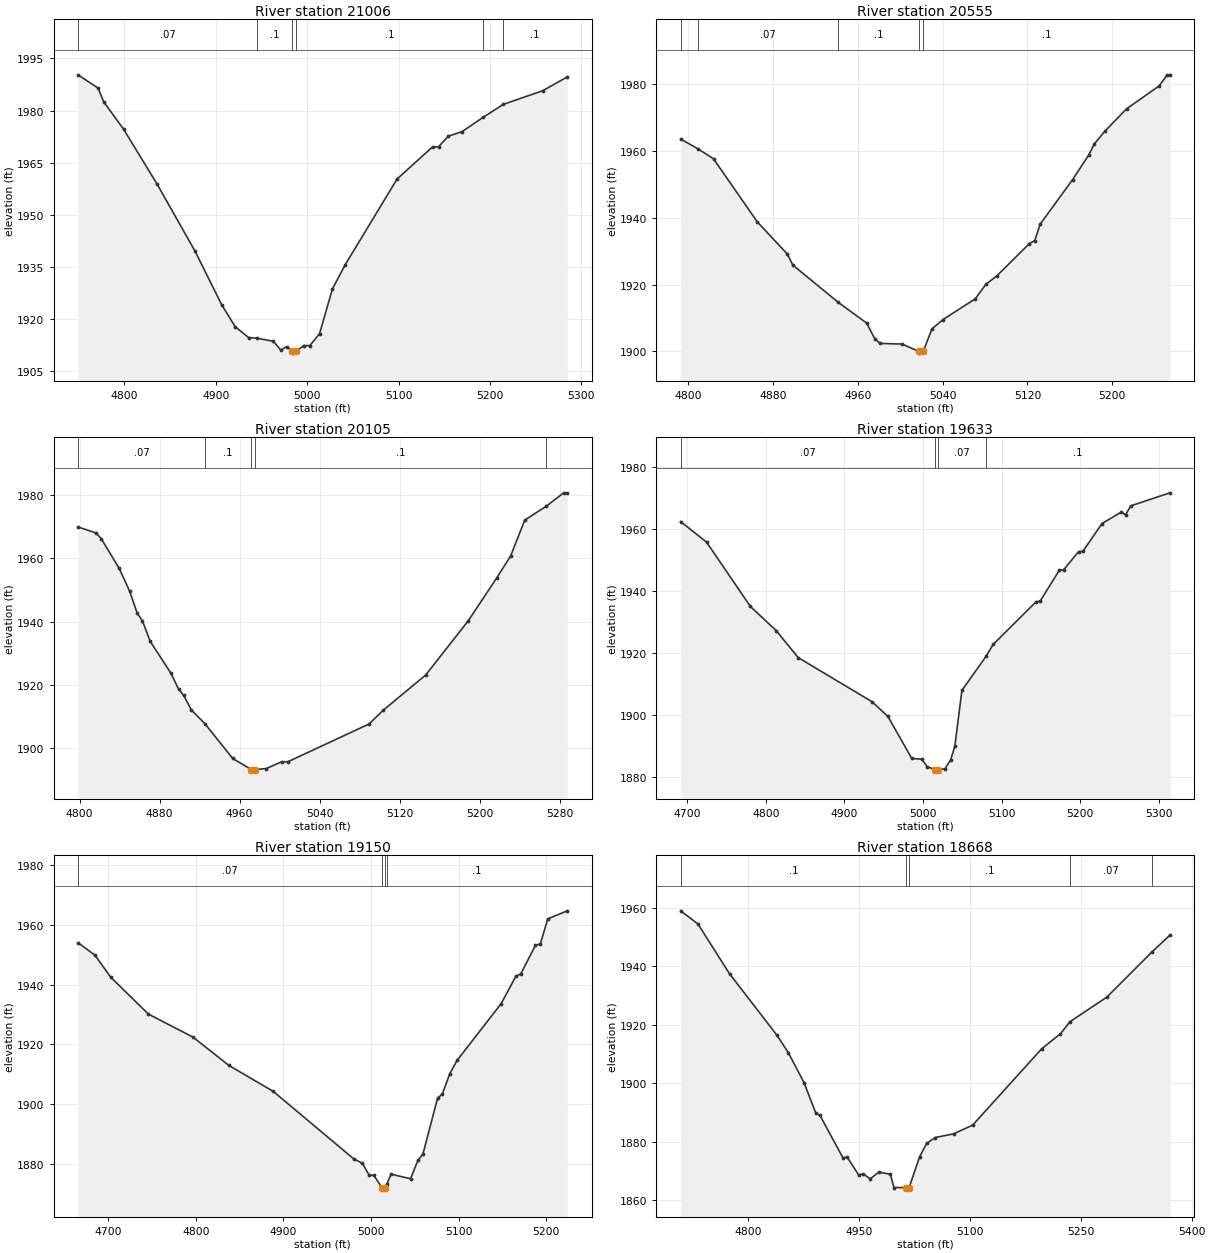
Type RM Length L Ch R = 1,21006,451,451,451
BEGIN DESCRIPTION:
Stream0030 46.0
END DESCRIPTION:
XS GIS Cut Line= 4
      1964575.01     13946125.01      1964425.00     13945925.00
      1964325.00     13945825.00      1964203.72     13945747.81
#Sta/Elev= 30
  4749.4 1990.28  4771.3 1986.48  4777.5 1982.51  4799.4 1974.57  4835.9 1958.84
  4877.5 1939.48  4906.7 1924.03  4921.3 1917.79  4935.9 1914.66  4945.3 1914.45
  4963.0 1913.59  4971.3 1911.02  4977.5 1912.04  4983.9 1910.67  4984.1 1910.17
  4987.9 1910.67  4996.3 1912.33  5003.0 1912.33  5013.6 1915.77  5027.7 1928.65
  5041.8 1935.67  5098.4 1960.29  5137.3 1969.56  5143.8 1969.56  5154.4 1972.61
  5169.6 1973.94  5192.7 1978.07  5214.4 1981.76  5257.7 1985.70  5284.6 1989.68
#Mann=6,-1,0
  4749.4    0.07       0  4945.3     0.1       0  4983.9    0.05       0
  4987.9     0.1       0  5192.7    0.07       0  5214.4     0.1       0
Bank Sta=4983.9,4987.9
Exp/Cntr=0.3,0.1

Type RM Length L Ch R = 1,20555,450,450,450
BEGIN DESCRIPTION:
Stream0030 45.0
END DESCRIPTION:
XS GIS Cut Line= 3
      1964775.01     13945875.03      1964725.00     13945675.00
      1964675.01     13945425.04
#Sta/Elev= 30
  4793.2 1963.54  4809.1 1960.71  4824.2 1957.62  4865.4 1938.77  4893.7 1929.14
  4898.9 1925.84  4941.9 1914.64  4968.5 1908.47  4976.2 1903.75  4981.3 1902.40
  5001.9 1902.20  5017.8 1899.99  5018.0 1899.49  5021.8 1899.99  5030.0 1906.73
  5040.2 1909.49  5070.8 1915.73  5081.0 1920.12  5091.2 1922.62  5121.8 1932.26
  5126.9 1933.16  5132.0 1938.06  5162.6 1951.43  5177.9 1958.83  5183.0 1962.07
  5193.1 1965.93  5213.5 1972.61  5244.1 1979.43  5251.8 1982.76  5254.3 1982.76
#Mann=5,-1,0
  4793.2     0.1       0  4809.1    0.07       0  4941.9     0.1       0
  5017.8    0.05       0  5021.8     0.1       0
Bank Sta=5017.8,5021.8
Exp/Cntr=0.3,0.1

Type RM Length L Ch R = 1,20105,472,472,472
BEGIN DESCRIPTION:
Stream0030 44.0
END DESCRIPTION:
XS GIS Cut Line= 3
      1965174.99     13945724.97      1965125.00     13945525.00
      1964924.98     13945324.98
#Sta/Elev= 30
  4798.5 1969.84  4816.5 1967.97  4821.7 1966.15  4839.7 1956.76  4850.0 1949.70
  4857.7 1942.62  4862.9 1940.25  4870.6 1933.81  4891.2 1923.81  4899.0 1918.73
  4904.1 1916.74  4911.9 1912.10  4925.4 1907.79  4953.1 1896.85  4971.7 1893.35
  4972.0 1892.85  4975.7 1893.35  4986.6 1893.66  5002.1 1895.80  5008.2 1895.80
  5089.5 1907.74  5103.6 1912.07  5146.0 1923.16  5188.5 1940.25  5216.8 1953.68
  5230.9 1960.71  5245.0 1972.00  5266.4 1976.37  5283.9 1980.61  5287.5 1980.61
#Mann=5,-1,0
  4798.5    0.07       0  4925.4     0.1       0  4971.7    0.05       0
  4975.7     0.1       0  5266.4    0.07       0
Bank Sta=4971.7,4975.7
Exp/Cntr=0.3,0.1

Type RM Length L Ch R = 1,19633,483,483,483
BEGIN DESCRIPTION:
Stream0030 43.0
END DESCRIPTION:
XS GIS Cut Line= 3
      1965525.00     13945574.98      1965475.00     13945275.00
      1965358.86     13944978.66
#Sta/Elev= 30
  4691.7 1962.44  4724.6 1955.83  4780.4 1935.07  4813.3 1927.27  4841.2 1918.58
  4935.0 1904.37  4955.3 1899.62  4985.7 1886.04  4998.5 1885.81  5005.4 1883.38
  5015.3 1882.46  5015.5 1881.96  5019.3 1882.46  5028.0 1882.70  5035.2 1885.65
  5040.5 1890.07  5049.5 1908.00  5080.1 1918.95  5089.4 1922.88  5143.7 1936.55
  5149.0 1936.78  5173.5 1946.79  5178.9 1946.89  5197.9 1952.76  5203.3 1952.84
  5227.7 1961.81  5252.2 1965.51  5257.6 1964.64  5264.3 1967.52  5314.1 1971.72
#Mann=4,-1,0
  4691.7    0.07       0  5015.3    0.05       0  5019.3    0.07       0
  5080.1     0.1       0
Bank Sta=5015.3,5019.3
Exp/Cntr=0.3,0.1

Type RM Length L Ch R = 1,19150,482,482,482
BEGIN DESCRIPTION:
Stream0030 42.0
END DESCRIPTION:
XS GIS Cut Line= 3
      1965862.55     13945604.03      1965925.00     13945275.00
      1966024.99     13945075.01
#Sta/Elev= 30
  4665.5 1954.05  4684.9 1949.85  4702.8 1942.50  4745.9 1930.13  4796.8 1922.40
  4837.6 1912.95  4888.4 1904.22  4980.0 1881.67  4990.2 1880.11  4997.9 1876.11
  5003.2 1876.11  5012.4 1871.97  5012.6 1871.47  5016.4 1871.97  5018.1 1873.17
  5022.8 1876.48  5045.1 1874.95  5053.5 1881.14  5059.1 1883.08  5075.9 1901.88
  5081.5 1903.43  5089.8 1910.08  5098.2 1914.61  5148.5 1933.62  5165.3 1942.80
  5170.9 1943.61  5187.7 1953.17  5193.3 1953.67  5201.7 1962.02  5224.0 1964.73
#Mann=4,-1,0
  4665.5    0.07       0  5012.4    0.05       0  5016.4    0.07       0
  5018.1     0.1       0
Bank Sta=5012.4,5016.4
Exp/Cntr=0.3,0.1

Type RM Length L Ch R = 1,18668,460,460,460
BEGIN DESCRIPTION:
Stream0030 41.0
END DESCRIPTION:
XS GIS Cut Line= 3
      1966525.00     13945624.99      1966375.00     13945375.00
      1966253.30     13945025.00
#Sta/Elev= 30
  4708.5 1958.97  4731.8 1954.50  4774.6 1937.47  4838.7 1916.47  4854.3 1910.42
  4875.6 1900.15  4891.2 1889.90  4897.0 1889.02  4928.1 1874.53  4934.0 1874.68
  4949.5 1868.62  4955.3 1869.03  4965.1 1867.34  4976.7 1869.63  4992.3 1868.90
  4997.1 1864.36  5013.6 1864.31  5013.8 1863.81  5017.6 1864.31  5031.8 1874.80
  5041.4 1879.46  5053.0 1881.46  5077.8 1882.71  5103.6 1885.69  5196.9 1911.76
  5222.4 1916.93  5235.5 1921.09  5285.0 1929.43  5346.2 1944.90  5370.6 1950.66
#Mann=5,-1,0
  4708.5     0.1       0  5013.6    0.05       0  5017.6     0.1       0
  5235.5    0.07       0  5346.2     0.1       0
Bank Sta=5013.6,5017.6
Exp/Cntr=0.3,0.1

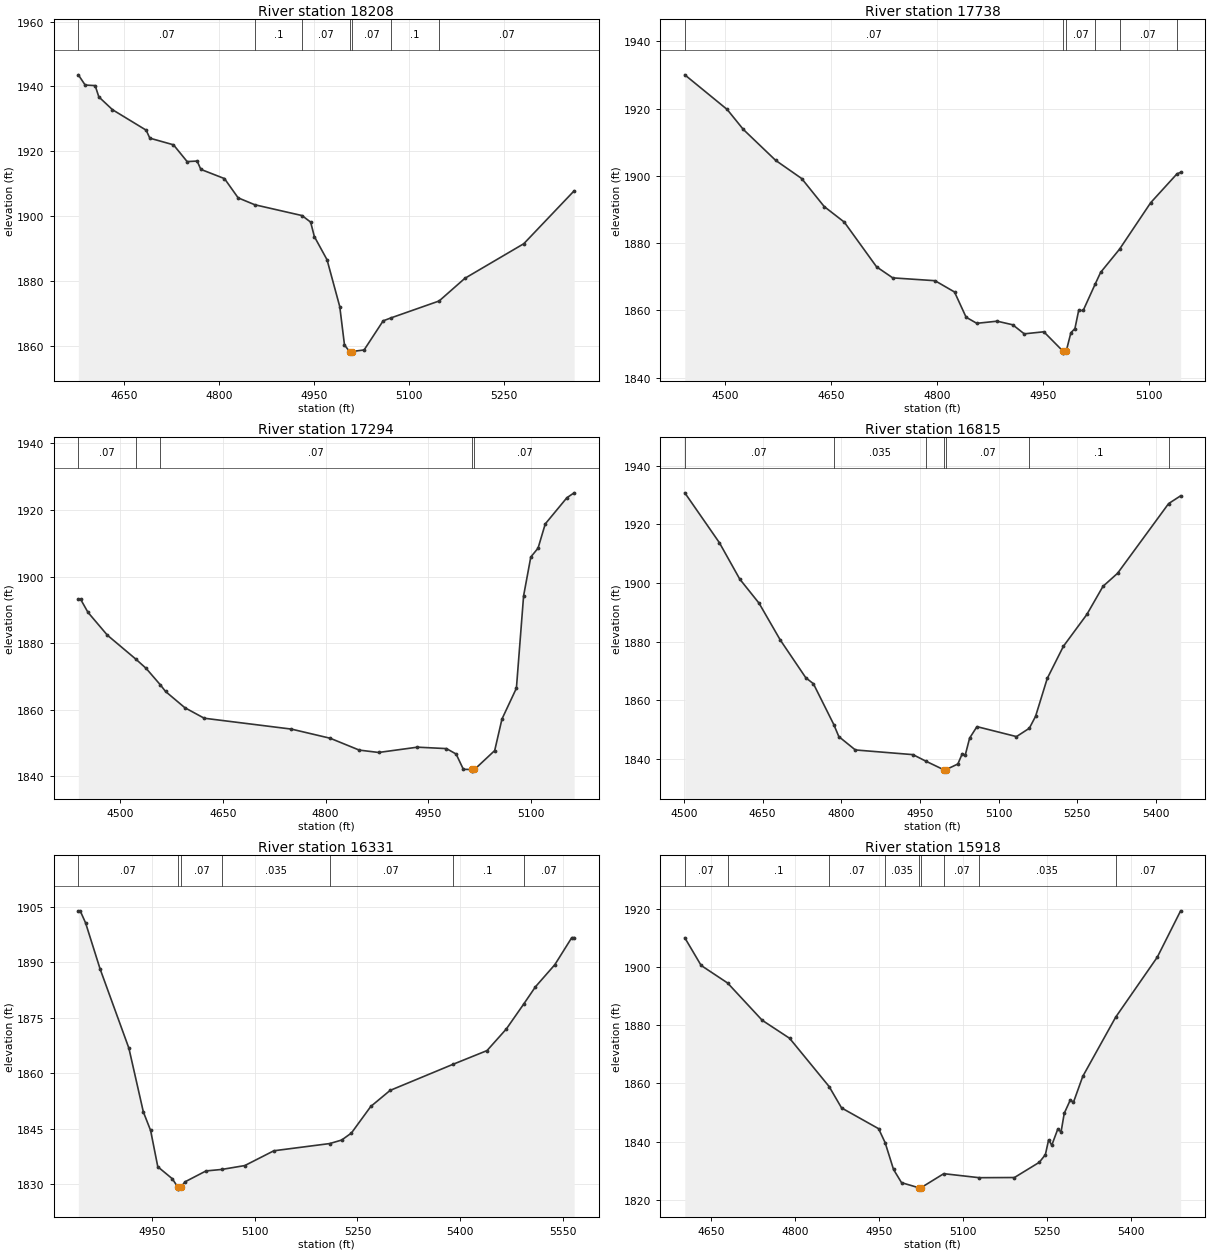
Type RM Length L Ch R = 1,18208,470,470,470
BEGIN DESCRIPTION:
Stream0030 40.0
END DESCRIPTION:
XS GIS Cut Line= 4
      1966644.98     13945609.92      1966787.06     13945361.32
      1966775.00     13945225.00      1966475.04     13945025.03
#Sta/Elev= 30
  4577.1 1943.59  4587.9 1940.44  4603.7 1940.27  4609.5 1936.80  4631.1 1932.85
  4684.3 1926.55  4690.1 1924.09  4727.5 1922.04  4749.1 1916.87  4764.9 1917.04
  4770.7 1914.48  4808.1 1911.64  4829.7 1905.71  4856.1 1903.58  4930.6 1900.26
  4944.3 1898.24  4950.1 1893.81  4970.2 1886.65  4990.3 1872.23  4997.8 1860.39
  5005.8 1858.40  5006.1 1857.90  5009.8 1858.40  5028.8 1858.88  5058.9 1867.84
  5071.6 1868.77  5147.3 1873.95  5188.1 1880.94  5281.2 1891.59  5360.8 1907.88
#Mann=7,-1,0
  4577.1    0.07       0  4856.1     0.1       0  4930.6    0.07       0
  5005.8    0.05       0  5009.8    0.07       0  5071.6     0.1       0
  5147.3    0.07       0
Bank Sta=5005.8,5009.8
Exp/Cntr=0.3,0.1

Type RM Length L Ch R = 1,17738,444,444,444
BEGIN DESCRIPTION:
Stream0030 39.0
END DESCRIPTION:
XS GIS Cut Line= 4
      1967224.99     13945224.98      1967092.52     13944940.11
      1966875.00     13944825.00      1966774.99     13944724.99
#Sta/Elev= 30
  4443.5 1930.01  4503.5 1919.71  4526.3 1913.79  4572.1 1904.59  4608.9 1899.20
  4640.8 1890.87  4669.2 1886.25  4714.9 1872.96  4737.8 1869.68  4797.6 1868.84
  4825.2 1865.49  4841.6 1857.99  4856.7 1856.18  4885.6 1856.81  4907.6 1855.74
  4923.9 1853.05  4951.6 1853.66  4979.1 1847.82  4979.3 1847.32  4983.2 1847.82
  4989.9 1853.38  4995.6 1854.60  5000.9 1859.99  5007.3 1859.99  5024.4 1867.89
  5032.0 1871.32  5058.8 1878.22  5102.8 1892.01  5140.1 1900.60  5145.2 1901.02
#Mann=6,-1,0
  4443.5    0.07       0  4979.1    0.05       0  4983.2    0.07       0
  5024.4     0.1       0  5058.8    0.07       0  5140.1     0.1       0
Bank Sta=4979.1,4983.2
Exp/Cntr=0.3,0.1

Type RM Length L Ch R = 1,17294,479,479,479
BEGIN DESCRIPTION:
Stream0030 38.0
END DESCRIPTION:
XS GIS Cut Line= 3
      1967524.99     13944874.99      1967125.00     13944475.00
      1966974.98     13944424.99
#Sta/Elev= 30
  4439.1 1893.11  4442.6 1893.11  4453.2 1889.24  4481.5 1882.38  4522.9 1875.21
  4538.1 1872.40  4558.8 1867.46  4566.4 1865.47  4594.6 1860.58  4622.9 1857.42
  4750.2 1854.15  4806.8 1851.40  4849.2 1847.84  4877.5 1847.13  4934.1 1848.72
  4976.5 1848.29  4990.6 1846.66  5001.2 1842.05  5013.3 1842.02  5013.5 1841.52
  5017.4 1842.02  5046.9 1847.70  5057.5 1857.17  5078.6 1866.45  5089.1 1894.22
  5099.6 1905.88  5110.2 1908.54  5120.7 1915.82  5152.3 1923.70  5162.9 1925.17
#Mann=5,-1,0
  4439.1    0.07       0  4522.9     0.1       0  4558.8    0.07       0
  5013.3    0.05       0  5017.4    0.07       0
Bank Sta=5013.3,5017.4
Exp/Cntr=0.3,0.1

Type RM Length L Ch R = 1,16815,484,484,484
BEGIN DESCRIPTION:
Stream0030 37.0
END DESCRIPTION:
XS GIS Cut Line= 3
      1967734.06     13944947.53      1967575.00     13944475.00
      1967375.00     13944075.00
#Sta/Elev= 30
  4501.5 1930.81  4567.5 1913.78  4606.3 1901.37  4643.1 1893.14  4683.5 1880.60
  4732.3 1867.68  4746.8 1865.64  4785.7 1851.71  4795.3 1847.59  4826.8 1843.03
  4936.8 1841.43  4962.0 1839.14  4995.2 1836.30  4995.5 1835.80  4999.6 1836.30
  5022.4 1838.24  5030.8 1841.76  5036.4 1841.22  5044.8 1847.07  5058.8 1850.99
  5134.2 1847.59  5158.7 1850.44  5170.6 1854.51  5192.9 1867.45  5223.7 1878.42
  5268.4 1889.28  5299.2 1898.88  5327.1 1903.36  5424.4 1927.14  5447.3 1929.79
#Mann=7,-1,0
  4501.5    0.07       0  4785.7   0.035       0  4962.0    0.07       0
  4995.2    0.05       0  4999.6    0.07       0  5158.7     0.1       0
  5424.4    0.07       0
Bank Sta=4995.2,4999.6
Exp/Cntr=0.3,0.1

Type RM Length L Ch R = 1,16331,413,413,413
BEGIN DESCRIPTION:
Stream0030 36.0
END DESCRIPTION:
XS GIS Cut Line= 3
      1968075.01     13944625.04      1968025.00     13944475.00
      1967625.03     13944075.03
#Sta/Elev= 30
  4842.5 1903.88  4845.2 1903.88  4853.1 1900.61  4874.2 1888.20  4916.3 1866.74
  4937.4 1849.51  4948.0 1844.50  4958.5 1834.68  4979.6 1831.45  4987.9 1829.13
  4988.2 1828.63  4992.3 1829.13  4998.0 1830.58  5028.9 1833.55  5051.8 1833.95
  5085.5 1835.00  5127.9 1839.00  5209.4 1840.95  5226.9 1841.90  5241.1 1843.79
  5269.4 1850.98  5297.6 1855.32  5388.8 1862.33  5439.1 1866.09  5467.3 1871.94
  5492.9 1878.74  5509.8 1883.34  5538.1 1889.32  5562.8 1896.63  5566.3 1896.63
#Mann=7,-1,0
  4842.5    0.07       0  4987.9    0.05       0  4992.3    0.07       0
  5051.8   0.035       0  5209.4    0.07       0  5388.8     0.1       0
  5492.9    0.07       0
Bank Sta=4987.9,4992.3
Exp/Cntr=0.3,0.1

Type RM Length L Ch R = 1,15918,472,472,472
BEGIN DESCRIPTION:
Stream0030 35.0
END DESCRIPTION:
XS GIS Cut Line= 3
      1968513.52     13944209.93      1968125.00     13944125.00
      1967689.62     13943902.79
#Sta/Elev= 30
  4602.8 1910.03  4632.0 1900.52  4679.3 1894.49  4741.2 1881.67  4790.2 1875.48
  4860.8 1858.91  4883.1 1851.55  4949.3 1844.41  4961.0 1839.60  4976.0 1830.40
  4990.3 1825.86  5020.7 1824.14  5021.0 1823.64  5025.2 1824.14  5065.8 1828.95
  5129.1 1827.57  5192.2 1827.63  5236.7 1832.87  5247.5 1835.49  5253.3 1840.60
  5258.9 1838.72  5269.9 1844.40  5275.5 1843.22  5281.2 1849.69  5292.1 1854.30
  5297.7 1853.49  5314.3 1862.38  5373.2 1882.75  5447.7 1903.40  5489.3 1919.29
#Mann=9,-1,0
  4602.8    0.07       0  4679.3     0.1       0  4860.8    0.07       0
  4961.0   0.035       0  5020.7   0.035       0  5025.2   0.035       0
  5065.8    0.07       0  5129.1   0.035       0  5373.2    0.07       0
Bank Sta=5020.7,5025.2
Exp/Cntr=0.3,0.1

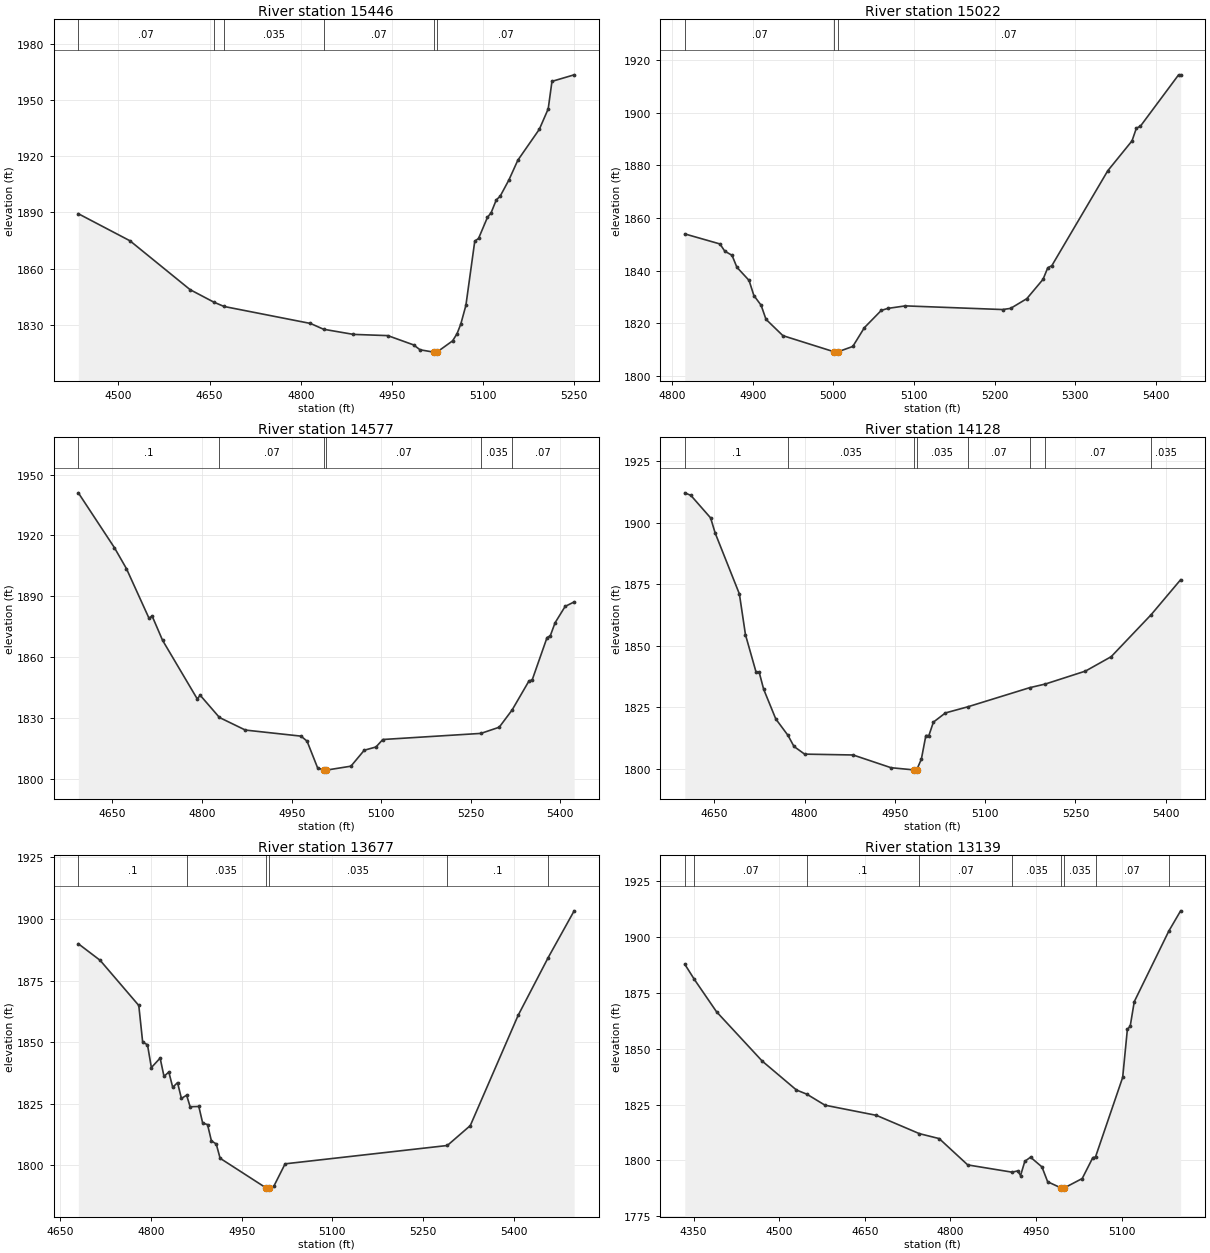
Type RM Length L Ch R = 1,15446,424,424,424
BEGIN DESCRIPTION:
Stream0030 34.0
END DESCRIPTION:
XS GIS Cut Line= 3
      1968425.02     13944125.02      1968025.00     13943725.00
      1967825.01     13943575.00
#Sta/Elev= 30
  4434.0 1889.30  4518.9 1874.86  4617.9 1848.76  4656.9 1842.10  4673.8 1839.78
  4815.9 1830.72  4837.5 1827.62  4886.6 1824.88  4943.1 1824.23  4985.6 1819.27
  4996.2 1816.66  5019.3 1815.38  5019.6 1814.88  5023.8 1815.38  5049.7 1821.43
  5057.0 1825.23  5063.2 1830.40  5071.6 1840.38  5086.2 1874.68  5092.4 1876.09
  5107.0 1887.32  5113.2 1889.90  5121.6 1896.71  5127.8 1898.55  5142.4 1907.36
  5157.0 1917.85  5192.4 1934.38  5207.0 1945.27  5213.2 1959.96  5249.7 1963.45
#Mann=6,-1,0
  4434.0    0.07       0  4656.9     0.1       0  4673.8   0.035       0
  4837.5    0.07       0  5019.3    0.05       0  5023.8    0.07       0
Bank Sta=5019.3,5023.8
Exp/Cntr=0.3,0.1

Type RM Length L Ch R = 1,15022,445,445,445
BEGIN DESCRIPTION:
Stream0030 33.0
END DESCRIPTION:
XS GIS Cut Line= 4
      1968475.02     13943675.03      1968375.00     13943525.00
      1968322.04     13943456.91      1967974.98     13943425.00
#Sta/Elev= 30
  4815.7 1853.95  4859.3 1850.14  4865.3 1847.41  4874.3 1845.83  4880.3 1841.31
  4895.4 1836.31  4901.4 1830.57  4910.4 1826.87  4916.4 1821.55  4937.4 1815.34
  5001.0 1809.21  5001.3 1808.71  5005.6 1809.21  5024.1 1811.24  5038.5 1818.38
  5059.4 1824.91  5067.5 1825.68  5089.3 1826.64  5209.9 1825.25  5219.9 1825.69
  5240.0 1829.38  5260.1 1836.71  5266.0 1841.11  5271.0 1841.89  5340.4 1877.91
  5370.5 1889.26  5375.9 1894.07  5380.9 1894.82  5428.3 1914.32  5430.8 1914.32
#Mann=3,-1,0
  4815.7    0.07       0  5001.0    0.05       0  5005.6    0.07       0
Bank Sta=5001,5005.6
Exp/Cntr=0.3,0.1

Type RM Length L Ch R = 1,14577,449,449,449
BEGIN DESCRIPTION:
Stream0030 32.0
END DESCRIPTION:
XS GIS Cut Line= 3
      1968825.01     13943075.00      1968425.00     13943125.00
      1968025.03     13943274.99
#Sta/Elev= 30
  4592.8 1940.99  4653.3 1913.92  4673.4 1903.60  4711.2 1879.14  4716.3 1880.31
  4733.9 1868.27  4791.9 1839.43  4796.9 1841.20  4829.1 1830.25  4872.5 1824.05
  4965.7 1821.06  4975.8 1818.59  4993.4 1805.49  5003.4 1804.31  5003.7 1803.81
  5008.1 1804.31  5049.3 1806.25  5071.6 1814.11  5091.2 1815.71  5102.7 1819.40
  5267.0 1822.41  5297.6 1825.45  5319.2 1833.95  5347.5 1848.29  5352.8 1848.75
  5377.7 1869.66  5383.1 1870.50  5391.1 1876.91  5408.0 1885.00  5423.1 1887.21
#Mann=6,-1,0
  4592.8     0.1       0  4829.1    0.07       0  5003.4    0.05       0
  5008.1    0.07       0  5267.0   0.035       0  5319.2    0.07       0
Bank Sta=5003.4,5008.1
Exp/Cntr=0.3,0.1

Type RM Length L Ch R = 1,14128,451,451,451
BEGIN DESCRIPTION:
Stream0030 31.0
END DESCRIPTION:
XS GIS Cut Line= 4
      1968675.02     13942675.00      1968275.00     13942725.00
      1968175.00     13942725.00      1967934.34     13942937.06
#Sta/Elev= 30
  4600.9 1912.22  4611.0 1911.17  4643.8 1902.01  4651.3 1895.90  4691.6 1871.07
  4701.7 1854.49  4719.3 1839.26  4724.4 1839.29  4731.9 1832.30  4752.1 1820.18
  4772.4 1813.49  4782.3 1809.00  4800.0 1805.87  4880.6 1805.52  4943.6 1800.34
  4981.5 1799.45  4981.9 1798.95  4986.2 1799.45  4994.0 1803.85  5001.5 1813.45
  5006.5 1813.45  5014.0 1818.90  5034.0 1822.64  5070.9 1825.11  5173.8 1832.90
  5200.1 1834.41  5266.7 1839.67  5309.4 1845.53  5375.8 1862.62  5424.8 1876.85
#Mann=8,-1,0
  4600.9     0.1       0  4772.4   0.035       0  4981.5   0.035       0
  4986.2   0.035       0  5070.9    0.07       0  5173.8   0.035       0
  5200.1    0.07       0  5375.8   0.035       0
Bank Sta=4981.5,4986.2
Exp/Cntr=0.3,0.1

Type RM Length L Ch R = 1,13677,538,538,538
BEGIN DESCRIPTION:
Stream0030 30.0
END DESCRIPTION:
XS GIS Cut Line= 3
      1968624.99     13942574.99      1968425.00     13942325.00
      1968025.03     13942025.02
#Sta/Elev= 30
  4679.9 1889.93  4715.9 1883.22  4779.9 1864.88  4786.3 1850.00  4794.3 1848.92
  4800.7 1839.67  4815.2 1843.52  4821.6 1836.10  4829.6 1837.87  4836.0 1831.65
  4844.0 1833.56  4850.4 1827.13  4859.0 1828.46  4864.8 1823.78  4879.2 1823.88
  4885.6 1817.11  4893.6 1816.54  4900.0 1809.92  4908.0 1808.66  4914.4 1802.86
  4990.4 1790.83  4990.8 1790.33  4995.2 1790.83  5003.2 1791.47  5021.9 1800.60
  5290.2 1808.04  5328.2 1816.12  5407.3 1860.85  5457.1 1884.34  5500.0 1903.30
#Mann=6,-1,0
  4679.9     0.1       0  4859.0   0.035       0  4990.4   0.035       0
  4995.2   0.035       0  5290.2     0.1       0  5457.1    0.07       0
Bank Sta=4990.4,4995.2
Exp/Cntr=0.3,0.1

Type RM Length L Ch R = 1,13139,365,365,365
BEGIN DESCRIPTION:
Stream0030 29.0
END DESCRIPTION:
XS GIS Cut Line= 3
      1968940.55     13941916.61      1968277.39     13941909.12
      1968074.95     13941874.99
#Sta/Elev= 30
  4334.6 1887.83  4351.3 1881.07  4390.2 1866.56  4470.2 1844.49  4530.2 1831.53
  4548.4 1829.67  4580.2 1824.74  4670.2 1820.20  4745.5 1812.01  4780.2 1809.79
  4830.2 1798.01  4907.9 1794.76  4917.7 1795.33  4922.7 1793.25  4930.2 1799.62
  4940.2 1801.47  4960.2 1797.11  4970.2 1790.46  4994.0 1787.67  4994.4 1787.17
  4999.0 1787.67  5030.7 1791.91  5049.3 1801.27  5054.0 1801.57  5101.6 1837.20
  5109.8 1858.65  5114.8 1860.15  5121.9 1871.09  5182.4 1902.69  5203.1 1911.75
#Mann=9,-1,0
  4334.6     0.1       0  4351.3    0.07       0  4548.4     0.1       0
  4745.5    0.07       0  4907.9   0.035       0  4994.0   0.035       0
  4999.0   0.035       0  5054.0    0.07       0  5182.4   0.035       0
Bank Sta=4994,4999
Exp/Cntr=0.3,0.1

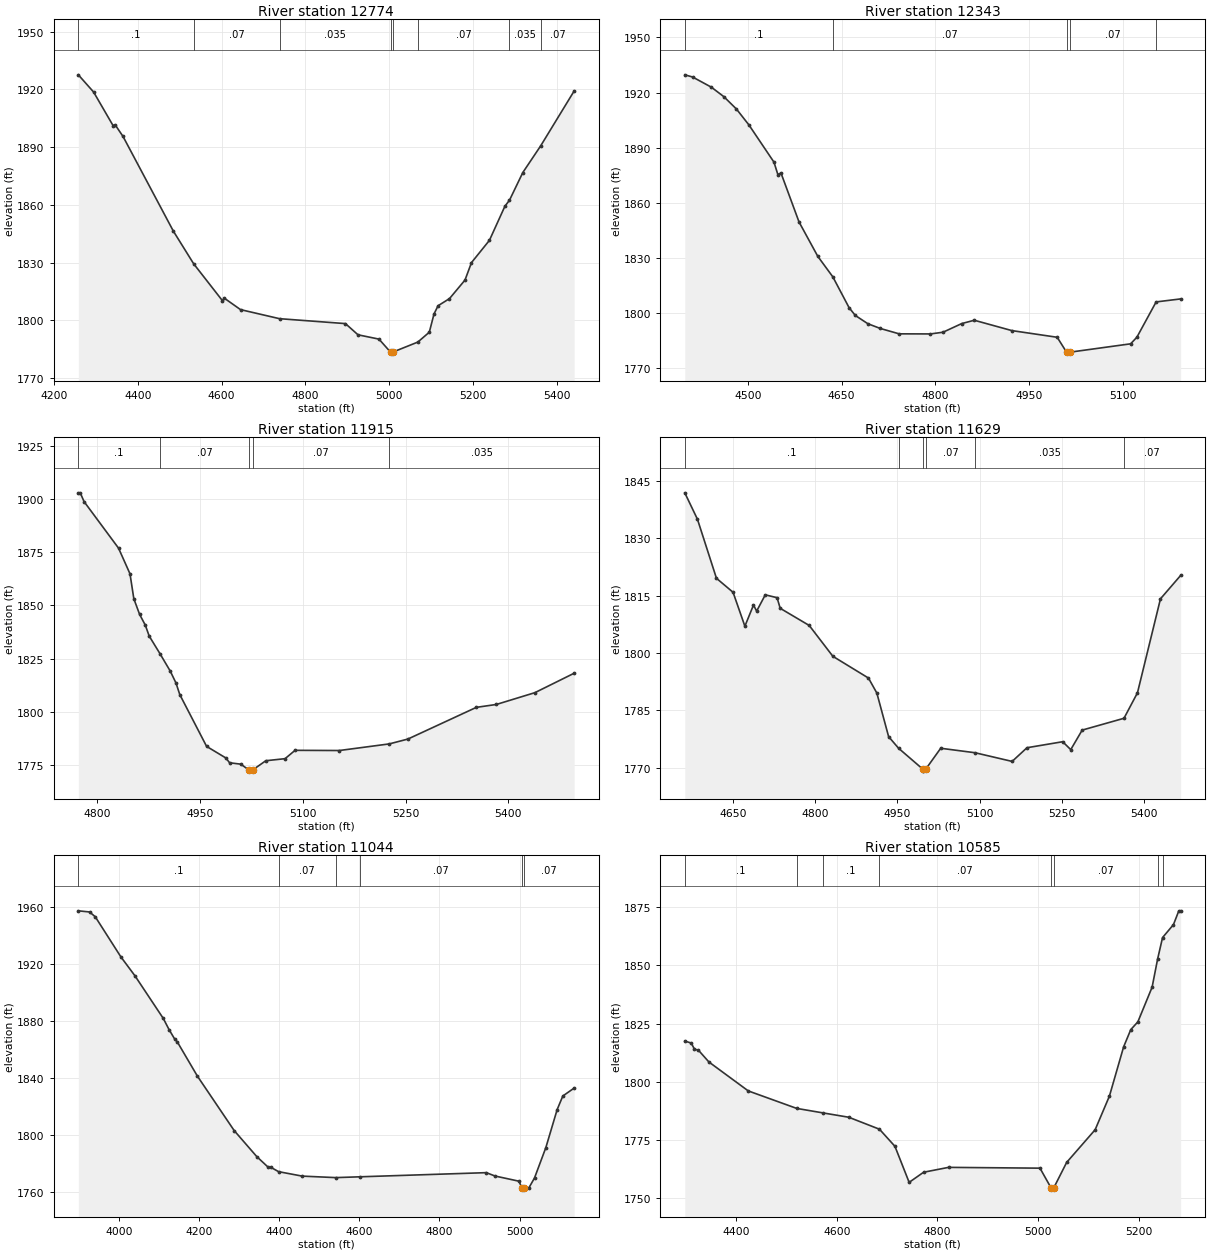
Type RM Length L Ch R = 1,12774,431,431,431
BEGIN DESCRIPTION:
Stream0030 28.0
END DESCRIPTION:
XS GIS Cut Line= 4
      1969111.42     13941546.79      1968375.00     13941575.00
      1968270.28     13941579.64      1967978.41     13941755.03
#Sta/Elev= 30
  4258.4 1927.61  4294.8 1918.67  4341.1 1901.28  4346.1 1901.66  4364.9 1895.62
  4485.0 1846.39  4533.4 1829.43  4601.8 1810.32  4606.8 1811.52  4645.1 1805.62
  4738.1 1800.91  4895.3 1798.35  4925.3 1792.53  4975.3 1790.29  5002.9 1783.51
  5003.3 1783.01  5007.9 1783.51  5067.9 1788.75  5095.3 1793.88  5106.5 1803.35
  5116.2 1807.64  5143.4 1811.33  5180.4 1820.97  5195.9 1830.05  5238.7 1841.63
  5275.6 1859.35  5286.5 1862.46  5318.3 1876.85  5361.0 1890.75  5440.7 1919.22
#Mann=8,-1,0
  4258.4     0.1       0  4533.4    0.07       0  4738.1   0.035       0
  5002.9   0.035       0  5007.9   0.035       0  5067.9    0.07       0
  5286.5   0.035       0  5361.0    0.07       0
Bank Sta=5002.9,5007.9
Exp/Cntr=0.3,0.1

Type RM Length L Ch R = 1,12343,428,428,428
BEGIN DESCRIPTION:
Stream0030 27.0
END DESCRIPTION:
XS GIS Cut Line= 3
      1969067.50     13941208.46      1968475.00     13941175.00
      1968275.04     13941175.00
#Sta/Elev= 30
  4399.0 1929.65  4411.5 1928.46  4441.6 1922.90  4461.6 1917.73  4481.6 1911.04
  4501.7 1902.33  4541.7 1882.10  4547.9 1875.38  4552.9 1876.21  4581.8 1849.54
  4611.8 1830.84  4635.9 1819.65  4661.9 1802.88  4671.9 1798.63  4692.0 1794.13
  4712.0 1791.55  4742.0 1788.64  4792.1 1788.59  4812.2 1789.52  4842.2 1794.24
  4862.2 1796.04  4922.3 1790.41  4994.9 1786.77  5009.9 1778.64  5010.3 1778.14
  5014.9 1778.64  5112.4 1783.21  5122.4 1786.80  5153.2 1806.02  5192.4 1807.65
#Mann=5,-1,0
  4399.0     0.1       0  4635.9    0.07       0  5009.9    0.05       0
  5014.9    0.07       0  5153.2   0.035       0
Bank Sta=5009.9,5014.9
Exp/Cntr=0.3,0.1

Type RM Length L Ch R = 1,11915,286,286,286
BEGIN DESCRIPTION:
Stream0030 26.0
END DESCRIPTION:
XS GIS Cut Line= 3
      1968574.96     13940675.02      1968375.00     13940775.00
      1967974.97     13941075.02
#Sta/Elev= 30
  4772.4 1902.90  4775.2 1902.90  4780.7 1898.81  4831.1 1876.90  4847.8 1864.85
  4853.4 1853.14  4861.8 1845.82  4870.2 1840.70  4875.8 1835.62  4891.4 1827.42
  4906.5 1819.18  4914.9 1813.57  4920.5 1808.10  4959.6 1783.79  4987.6 1778.37
  4993.2 1776.09  5009.5 1775.44  5021.5 1772.67  5021.9 1772.17  5026.6 1772.67
  5046.0 1777.05  5074.1 1778.02  5088.7 1781.94  5153.3 1781.85  5226.2 1784.96
  5253.3 1787.23  5353.3 1802.13  5382.4 1803.48  5438.7 1809.03  5496.0 1818.16
#Mann=5,-1,0
  4772.4     0.1       0  4891.4    0.07       0  5021.5    0.05       0
  5026.6    0.07       0  5226.2   0.035       0
Bank Sta=5021.5,5026.6
Exp/Cntr=0.3,0.1

Type RM Length L Ch R = 1,11629,585,585,585
BEGIN DESCRIPTION:
Stream0030 25.0
END DESCRIPTION:
XS GIS Cut Line= 3
      1968424.99     13940175.03      1968203.63     13940556.28
      1967824.96     13940825.03
#Sta/Elev= 30
  4561.7 1841.88  4584.8 1834.97  4619.5 1819.53  4649.8 1815.87  4671.4 1807.00
  4687.1 1812.53  4692.9 1810.95  4708.6 1815.20  4730.1 1814.46  4735.9 1811.68
  4788.9 1807.19  4832.0 1799.13  4897.0 1793.44  4912.3 1789.52  4933.8 1778.12
  4952.0 1775.08  4996.4 1769.60  4996.8 1769.10  5001.5 1769.60  5028.9 1775.08
  5091.6 1773.91  5159.3 1771.64  5186.4 1775.22  5251.6 1776.79  5266.3 1774.72
  5287.2 1779.83  5363.5 1782.92  5388.1 1789.58  5430.1 1814.16  5466.9 1820.27
#Mann=6,-1,0
  4561.7     0.1       0  4952.0    0.07       0  4996.4    0.05       0
  5001.5    0.07       0  5091.6   0.035       0  5363.5    0.07       0
Bank Sta=4996.4,5001.5
Exp/Cntr=0.3,0.1

Type RM Length L Ch R = 1,11044,459,459,459
BEGIN DESCRIPTION:
Stream0030 24.0
END DESCRIPTION:
XS GIS Cut Line= 3
      1968525.00     13939775.00      1967725.00     13940525.00
      1967625.00     13940625.00
#Sta/Elev= 30
  3898.3 1957.57  3926.4 1956.77  3940.6 1953.39  4004.5 1925.26  4039.7 1911.96
  4110.5 1882.01  4124.7 1874.28  4138.9 1867.56  4145.7 1865.45  4195.5 1841.60
  4287.4 1803.36  4344.0 1785.03  4372.3 1777.63  4379.2 1777.53  4398.3 1774.51
  4457.3 1771.38  4541.0 1770.33  4600.7 1770.89  4917.0 1773.81  4938.5 1771.47
  4998.4 1767.82  5006.4 1762.75  5006.8 1762.25  5011.6 1762.75  5023.2 1763.13
  5037.3 1770.07  5065.6 1791.39  5093.9 1818.11  5108.0 1827.61  5136.3 1833.17
#Mann=6,-1,0
  3898.3     0.1       0  4398.3    0.07       0  4541.0     0.1       0
  4600.7    0.07       0  5006.4    0.05       0  5011.6    0.07       0
Bank Sta=5006.4,5011.6
Exp/Cntr=0.3,0.1

Type RM Length L Ch R = 1,10585,442,442,442
BEGIN DESCRIPTION:
Stream0030 23.0
END DESCRIPTION:
XS GIS Cut Line= 3
      1968019.73     13939582.18      1967575.00     13940125.00
      1967374.98     13940325.02
#Sta/Elev= 30
  4298.3 1817.47  4311.0 1816.63  4317.5 1814.00  4325.4 1813.55  4346.2 1808.50
  4424.4 1796.09  4520.5 1788.60  4572.7 1786.67  4623.9 1784.81  4684.9 1779.67
  4715.6 1772.34  4743.8 1756.89  4772.5 1761.23  4822.0 1763.32  5003.6 1762.98
  5025.7 1754.49  5026.1 1753.99  5030.9 1754.49  5056.6 1765.45  5113.2 1779.47
  5141.5 1793.87  5169.7 1814.98  5183.9 1822.37  5198.0 1825.71  5226.3 1840.59
  5237.1 1852.53  5247.0 1861.84  5268.7 1867.41  5279.3 1873.31  5282.9 1873.31
#Mann=8,-1,0
  4298.3     0.1       0  4520.5    0.07       0  4572.7     0.1       0
  4684.9    0.07       0  5025.7    0.05       0  5030.9    0.07       0
  5237.1   0.035       0  5247.0    0.07       0
Bank Sta=5025.7,5030.9
Exp/Cntr=0.3,0.1