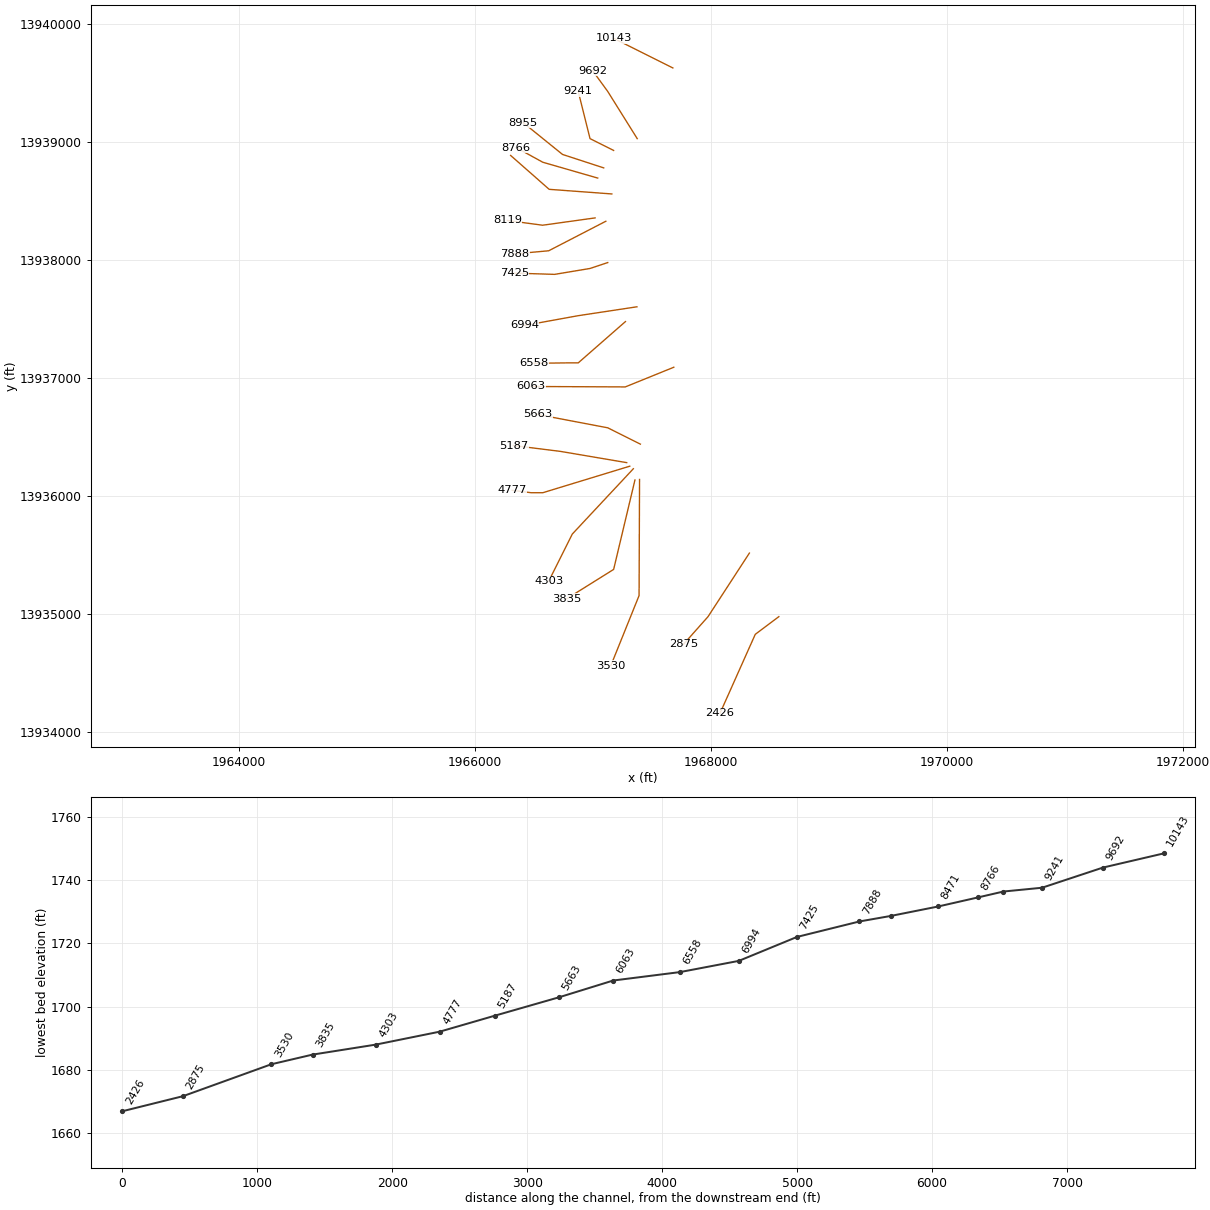
HEC-RAS study Stream0030.prj: Stream0030 Base Level Engineering

--- Stream0030.g01 (geometry) --- (continued)

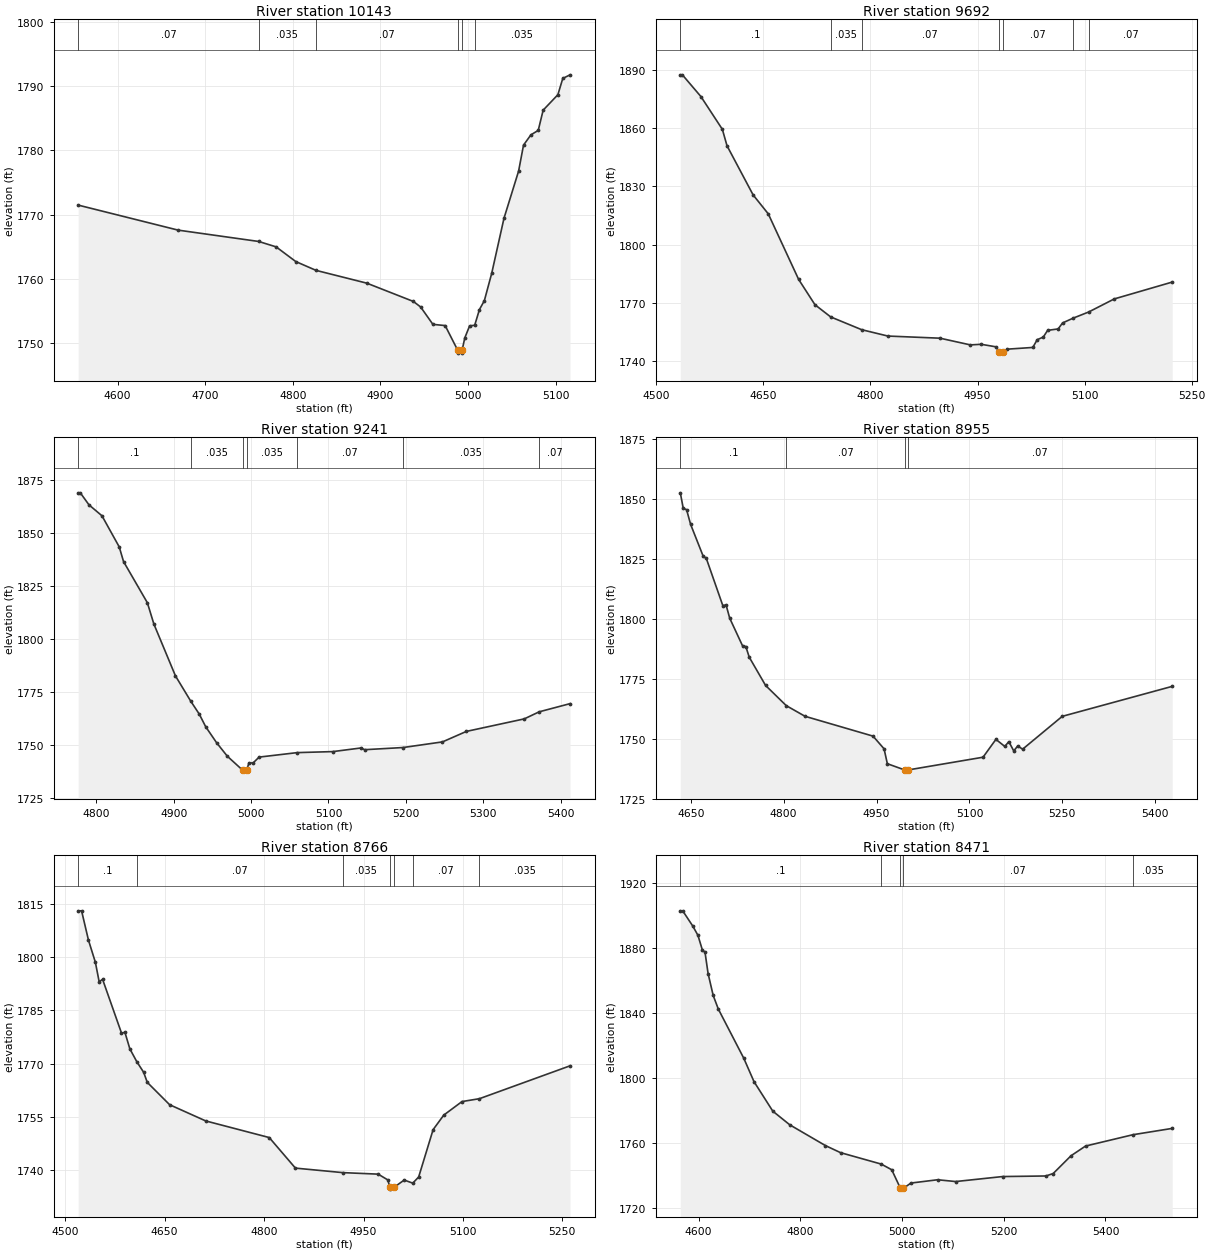
Type RM Length L Ch R = 1,10143,451,451,451
BEGIN DESCRIPTION:
Stream0030 22.0
END DESCRIPTION:
XS GIS Cut Line= 3
      1967677.06     13939623.92      1967275.00     13939825.00
      1967175.04     13939874.98
#Sta/Elev= 30
  4555.0 1771.49  4669.1 1767.60  4761.0 1765.84  4780.9 1765.00  4803.3 1762.72
  4826.4 1761.35  4884.4 1759.36  4937.5 1756.52  4945.8 1755.66  4959.8 1752.96
  4973.8 1752.77  4987.9 1748.99  4988.3 1748.49  4992.8 1748.49  4993.2 1748.99
  4996.2 1750.86  5001.7 1752.73  5007.5 1752.82  5012.9 1755.26  5018.5 1756.64
  5026.9 1760.89  5040.9 1769.44  5057.6 1776.78  5063.2 1780.81  5071.6 1782.40
  5080.0 1783.10  5085.6 1786.24  5102.4 1788.64  5108.0 1791.17  5116.3 1791.73
#Mann=6,-1,0
  4555.0    0.07       0  4761.0   0.035       0  4826.4    0.07       0
  4987.9    0.05       0  4993.2    0.07       0  5007.5   0.035       0
Bank Sta=4987.9,4993.2
Exp/Cntr=0.3,0.1

Type RM Length L Ch R = 1,9692,451,451,451
BEGIN DESCRIPTION:
Stream0030 21.0
END DESCRIPTION:
XS GIS Cut Line= 3
      1967374.98     13939025.03      1967125.00     13939425.00
      1966996.98     13939600.63
#Sta/Elev= 30
  4533.7 1887.55  4536.6 1887.55  4562.6 1876.32  4592.6 1859.43  4599.1 1850.97
  4635.7 1825.59  4656.9 1815.84  4699.4 1782.05  4722.3 1768.96  4744.3 1762.68
  4787.7 1756.09  4824.4 1752.81  4897.5 1751.70  4939.9 1748.25  4955.2 1748.55
  4976.5 1747.21  4979.7 1744.50  4980.1 1744.00  4985.0 1744.50  4991.8 1746.05
  5027.4 1746.93  5033.6 1750.93  5042.1 1752.29  5048.2 1755.75  5062.9 1756.48
  5069.1 1759.57  5083.7 1762.01  5105.7 1765.22  5141.5 1771.96  5222.7 1780.65
#Mann=7,-1,0
  4533.7     0.1       0  4744.3   0.035       0  4787.7    0.07       0
  4979.7    0.05       0  4985.0    0.07       0  5083.7   0.035       0
  5105.7    0.07       0
Bank Sta=4979.7,4985
Exp/Cntr=0.3,0.1

Type RM Length L Ch R = 1,9241,286,286,286
BEGIN DESCRIPTION:
Stream0030 20.0
END DESCRIPTION:
XS GIS Cut Line= 3
      1967175.02     13938924.99      1966975.00     13939025.00
      1966875.01     13939424.96
#Sta/Elev= 30
  4776.4 1868.99  4779.2 1868.99  4790.4 1863.32  4807.2 1858.15  4829.5 1843.48
  4835.1 1836.54  4865.9 1817.10  4874.3 1807.06  4902.2 1782.58  4922.1 1770.57
  4933.0 1764.53  4941.3 1758.57  4955.3 1751.07  4969.3 1744.64  4988.9 1738.12
  4989.4 1737.62  4994.3 1738.12  4997.2 1741.49  5002.6 1741.49  5010.3 1744.24
  5059.7 1746.36  5105.7 1746.84  5141.8 1748.54  5146.9 1747.74  5196.4 1748.76
  5247.4 1751.42  5278.3 1756.37  5353.1 1762.28  5372.4 1765.62  5412.3 1769.48
#Mann=7,-1,0
  4776.4     0.1       0  4922.1   0.035       0  4988.9   0.035       0
  4994.3   0.035       0  5059.7    0.07       0  5196.4   0.035       0
  5372.4    0.07       0
Bank Sta=4988.9,4994.3
Exp/Cntr=0.3,0.1

Type RM Length L Ch R = 1,8955,189,189,189
BEGIN DESCRIPTION:
Mapping XS d2f7218e
END DESCRIPTION:
XS GIS Cut Line= 3
      1967090.83     13938777.26      1966742.04     13938891.13
      1966409.58     13939159.71
#Sta/Elev= 30
  4633.1 1852.44  4637.9 1845.92  4643.2 1845.44  4649.8 1839.24  4669.8 1826.17
  4675.1 1825.09  4701.7 1805.45  4707.0 1805.69  4712.9 1800.16  4733.6 1788.65
  4738.9 1788.34  4744.4 1783.92  4770.8 1772.14  4804.2 1763.72  4834.5 1759.28
  4944.3 1751.01  4962.1 1745.72  4967.4 1739.51  4995.3 1736.92  4995.7 1736.42
  5001.1 1736.92  5121.9 1742.22  5142.7 1749.66  5157.1 1746.70  5163.5 1748.72
  5171.5 1744.85  5177.9 1746.89  5185.9 1745.58  5249.8 1759.26  5427.4 1771.76
#Mann=4,-1,0
  4633.1     0.1       0  4804.2    0.07       0  4995.3    0.05       0
  5001.1    0.07       0
Bank Sta=4995.3,5001.1
Exp/Cntr=0.3,0.1

Type RM Length L Ch R = 1,8766,295,295,295
BEGIN DESCRIPTION:
Stream0030 19.0
END DESCRIPTION:
XS GIS Cut Line= 3
      1967039.95     13938691.06      1966575.00     13938825.00
      1966348.63     13938949.28
#Sta/Elev= 30
  4519.5 1813.11  4524.7 1813.11  4535.1 1804.82  4545.5 1798.59  4551.2 1793.10
  4556.4 1793.76  4584.9 1778.61  4590.1 1778.80  4597.5 1774.15  4608.1 1770.49
  4618.3 1767.54  4623.8 1764.69  4657.5 1758.38  4712.0 1753.80  4807.8 1749.11
  4847.3 1740.48  4918.7 1739.21  4972.1 1738.78  4986.5 1737.17  4990.0 1735.05
  4990.5 1734.55  4995.9 1735.05  5011.4 1737.11  5024.3 1736.24  5033.2 1737.97
  5055.0 1751.34  5071.1 1755.45  5098.6 1759.27  5124.9 1760.08  5261.6 1769.36
#Mann=7,-1,0
  4519.5     0.1       0  4608.1    0.07       0  4918.7   0.035       0
  4990.0   0.035       0  4995.9   0.035       0  5024.3    0.07       0
  5124.9   0.035       0
Bank Sta=4990,4995.9
Exp/Cntr=0.3,0.1

Type RM Length L Ch R = 1,8471,352,352,352
BEGIN DESCRIPTION:
Mapping XS d6a60bea
END DESCRIPTION:
XS GIS Cut Line= 3
      1967159.47     13938556.52      1966628.71     13938595.60
      1966302.22     13938882.75
#Sta/Elev= 30
  4564.2 1903.06  4568.9 1903.06  4588.7 1893.68  4598.8 1888.01  4607.7 1878.81
  4612.7 1877.67  4618.8 1864.45  4628.8 1850.98  4638.9 1842.58  4689.0 1812.25
  4709.1 1797.85  4746.0 1779.70  4779.3 1771.30  4849.4 1758.51  4879.2 1754.14
  4959.2 1747.10  4979.8 1743.61  4996.9 1732.18  4997.4 1731.68  5002.8 1732.18
  5017.5 1735.42  5070.0 1737.45  5105.5 1736.35  5197.6 1739.42  5282.9 1739.78
  5297.2 1741.29  5332.3 1752.25  5360.8 1758.21  5454.0 1765.19  5531.2 1769.08
#Mann=5,-1,0
  4564.2     0.1       0  4959.2    0.07       0  4996.9    0.05       0
  5002.8    0.07       0  5454.0   0.035       0
Bank Sta=4996.9,5002.8
Exp/Cntr=0.3,0.1

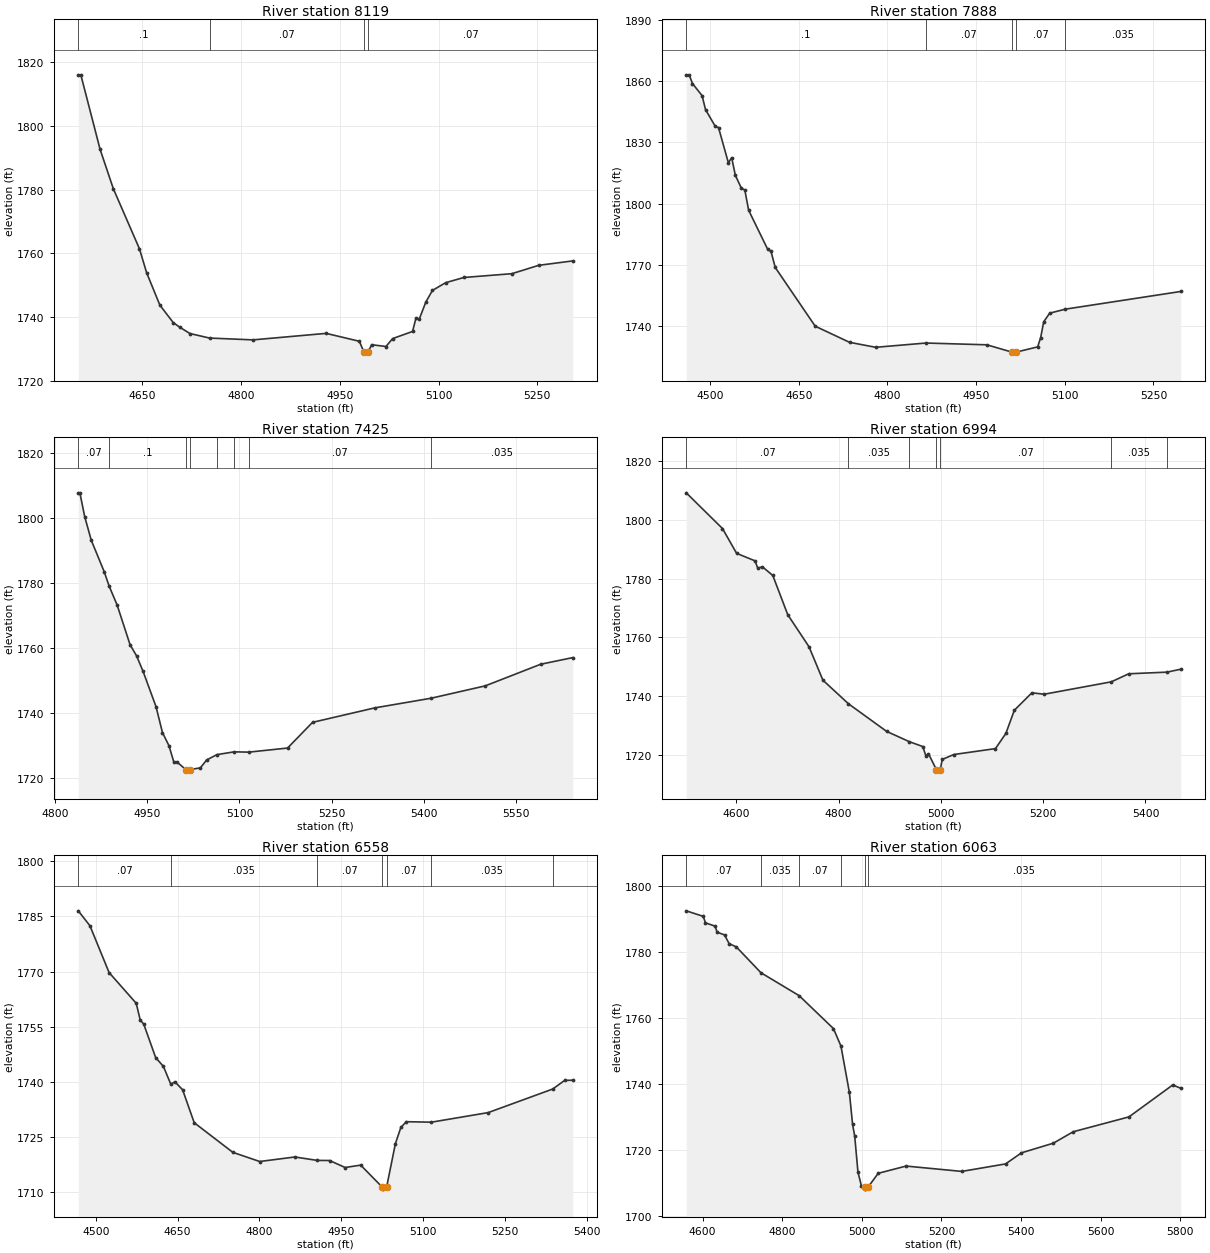
Type RM Length L Ch R = 1,8119,231,231,231
BEGIN DESCRIPTION:
Stream0030 18.0
END DESCRIPTION:
XS GIS Cut Line= 3
      1967017.76     13938353.43      1966573.28     13938291.49
      1966273.94     13938331.68
#Sta/Elev= 30
  4552.9 1816.02  4556.8 1816.02  4586.0 1792.66  4606.2 1780.25  4645.8 1761.43
  4656.7 1753.92  4676.8 1743.75  4697.0 1738.29  4707.1 1736.80  4722.5 1734.83
  4752.2 1733.41  4818.2 1732.84  4929.3 1734.88  4979.7 1732.40  4986.3 1729.18
  4986.8 1728.68  4993.4 1729.18  4998.3 1731.32  5020.1 1730.76  5030.2 1733.24
  5060.5 1735.48  5065.6 1739.60  5070.6 1739.31  5080.7 1744.73  5090.7 1748.36
  5110.9 1750.80  5138.5 1752.42  5211.3 1753.61  5252.2 1756.24  5303.7 1757.62
#Mann=4,-1,0
  4552.9     0.1       0  4752.2    0.07       0  4986.3    0.05       0
  4993.4    0.07       0
Bank Sta=4986.3,4993.4
Exp/Cntr=0.3,0.1

Type RM Length L Ch R = 1,7888,463,463,463
BEGIN DESCRIPTION:
Stream0030 17.0
END DESCRIPTION:
XS GIS Cut Line= 3
      1967108.83     13938325.08      1966625.00     13938075.00
      1966334.26     13938048.31
#Sta/Elev= 30
  4459.5 1863.09  4464.5 1863.09  4470.0 1858.84  4486.3 1852.92  4492.1 1846.09
  4508.7 1837.86  4514.1 1837.31  4530.8 1820.05  4536.4 1822.56  4542.6 1813.93
  4553.0 1807.51  4558.6 1806.78  4565.1 1796.83  4597.3 1777.74  4602.9 1776.75
  4610.1 1768.84  4677.7 1740.12  4735.8 1732.23  4780.0 1729.79  4865.1 1731.88
  4968.1 1731.01  5010.6 1727.44  5011.1 1726.94  5017.7 1727.44  5054.1 1729.99
  5059.1 1734.46  5064.4 1742.31  5074.4 1746.48  5100.9 1748.45  5296.1 1757.10
#Mann=5,-1,0
  4459.5     0.1       0  4865.1    0.07       0  5010.6    0.05       0
  5017.7    0.07       0  5100.9   0.035       0
Bank Sta=5010.6,5017.7
Exp/Cntr=0.3,0.1

Type RM Length L Ch R = 1,7425,431,431,431
BEGIN DESCRIPTION:
Stream0030 16.0
END DESCRIPTION:
XS GIS Cut Line= 4
      1967125.00     13937975.00      1966975.00     13937925.00
      1966675.00     13937875.00      1966332.83     13937885.74
#Sta/Elev= 30
  4837.7 1807.74  4840.3 1807.74  4848.2 1800.40  4858.8 1793.17  4879.9 1783.45
  4887.9 1779.04  4901.0 1773.16  4922.0 1760.97  4932.6 1757.53  4943.1 1752.79
  4964.2 1741.91  4974.7 1733.92  4985.3 1729.86  4993.2 1724.86  4998.4 1724.86
  5012.5 1722.54  5013.0 1722.04  5019.7 1722.54  5036.4 1723.04  5046.5 1725.46
  5063.3 1727.12  5091.4 1727.98  5115.3 1727.89  5178.3 1729.15  5218.9 1737.06
  5320.0 1741.51  5411.6 1744.48  5500.1 1748.30  5590.1 1754.95  5642.3 1757.00
#Mann=8,-1,0
  4837.7    0.07       0  4887.9     0.1       0  5012.5    0.05       0
  5019.7     0.1       0  5063.3    0.07       0  5091.4     0.1       0
  5115.3    0.07       0  5411.6   0.035       0
Bank Sta=5012.5,5019.7
Exp/Cntr=0.3,0.1

Type RM Length L Ch R = 1,6994,436,436,436
BEGIN DESCRIPTION:
Stream0030 15.0
END DESCRIPTION:
XS GIS Cut Line= 3
      1967372.43     13937600.26      1966875.00     13937525.00
      1966418.67     13937442.06
#Sta/Elev= 30
  4502.0 1809.23  4572.9 1797.07  4600.5 1788.63  4636.7 1786.05  4641.7 1783.61
  4651.1 1784.03  4671.3 1781.08  4700.5 1767.73  4742.1 1756.81  4769.3 1745.42
  4819.3 1737.39  4893.8 1728.00  4938.4 1724.48  4964.6 1722.83  4970.7 1719.61
  4975.7 1720.39  4991.2 1714.96  4991.7 1714.46  4998.8 1714.96  5002.6 1718.44
  5025.4 1720.12  5106.7 1722.13  5127.1 1727.32  5143.6 1735.19  5177.9 1741.13
  5202.1 1740.65  5333.2 1744.87  5367.3 1747.61  5442.1 1748.17  5468.9 1749.16
#Mann=7,-1,0
  4502.0    0.07       0  4819.3   0.035       0  4938.4    0.07       0
  4991.2    0.05       0  4998.8    0.07       0  5333.2   0.035       0
  5442.1    0.07       0
Bank Sta=4991.2,4998.8
Exp/Cntr=0.3,0.1

Type RM Length L Ch R = 1,6558,495,495,495
BEGIN DESCRIPTION:
Stream0030 14.0
END DESCRIPTION:
XS GIS Cut Line= 4
      1967275.03     13937475.03      1966875.00     13937125.00
      1966775.00     13937125.00      1966499.97     13937121.44
#Sta/Elev= 30
  4467.8 1786.48  4489.2 1782.43  4524.3 1769.72  4574.1 1761.37  4581.3 1756.88
  4587.9 1755.70  4609.7 1746.64  4624.0 1744.21  4637.5 1739.39  4644.9 1740.06
  4659.1 1737.90  4680.4 1728.94  4751.2 1720.90  4800.5 1718.41  4865.0 1719.64
  4905.9 1718.71  4928.6 1718.68  4957.1 1716.78  4985.6 1717.43  5025.5 1711.41
  5026.0 1710.91  5033.1 1711.41  5049.3 1723.28  5059.3 1727.66  5069.3 1729.22
  5115.3 1729.09  5219.4 1731.69  5337.7 1738.09  5359.4 1740.41  5374.4 1740.50
#Mann=7,-1,0
  4467.8    0.07       0  4637.5   0.035       0  4905.9    0.07       0
  5025.5    0.05       0  5033.1    0.07       0  5115.3   0.035       0
  5337.7    0.07       0
Bank Sta=5025.5,5033.1
Exp/Cntr=0.3,0.1

Type RM Length L Ch R = 1,6063,400,400,400
BEGIN DESCRIPTION:
Stream0030 13.0
END DESCRIPTION:
XS GIS Cut Line= 3
      1967684.82     13937088.08      1967273.77     13936921.38
      1966475.04     13936925.00
#Sta/Elev= 30
  4558.8 1792.58  4601.6 1790.90  4607.0 1788.95  4631.1 1787.94  4636.5 1786.11
  4655.2 1785.27  4666.5 1782.64  4684.7 1781.64  4746.5 1773.82  4842.5 1766.87
  4928.6 1756.90  4947.5 1751.61  4968.7 1737.56  4976.7 1727.88  4982.1 1724.29
  4990.2 1713.45  4999.0 1709.16  5007.3 1708.74  5007.8 1708.24  5015.0 1708.74
  5041.1 1713.03  5111.1 1715.23  5251.1 1713.61  5361.1 1715.88  5401.1 1719.24
  5481.1 1722.16  5531.1 1725.63  5671.1 1730.13  5781.1 1739.81  5801.1 1738.82
#Mann=6,-1,0
  4558.8    0.07       0  4746.5   0.035       0  4842.5    0.07       0
  4947.5   0.035       0  5007.3   0.035       0  5015.0   0.035       0
Bank Sta=5007.3,5015
Exp/Cntr=0.3,0.1

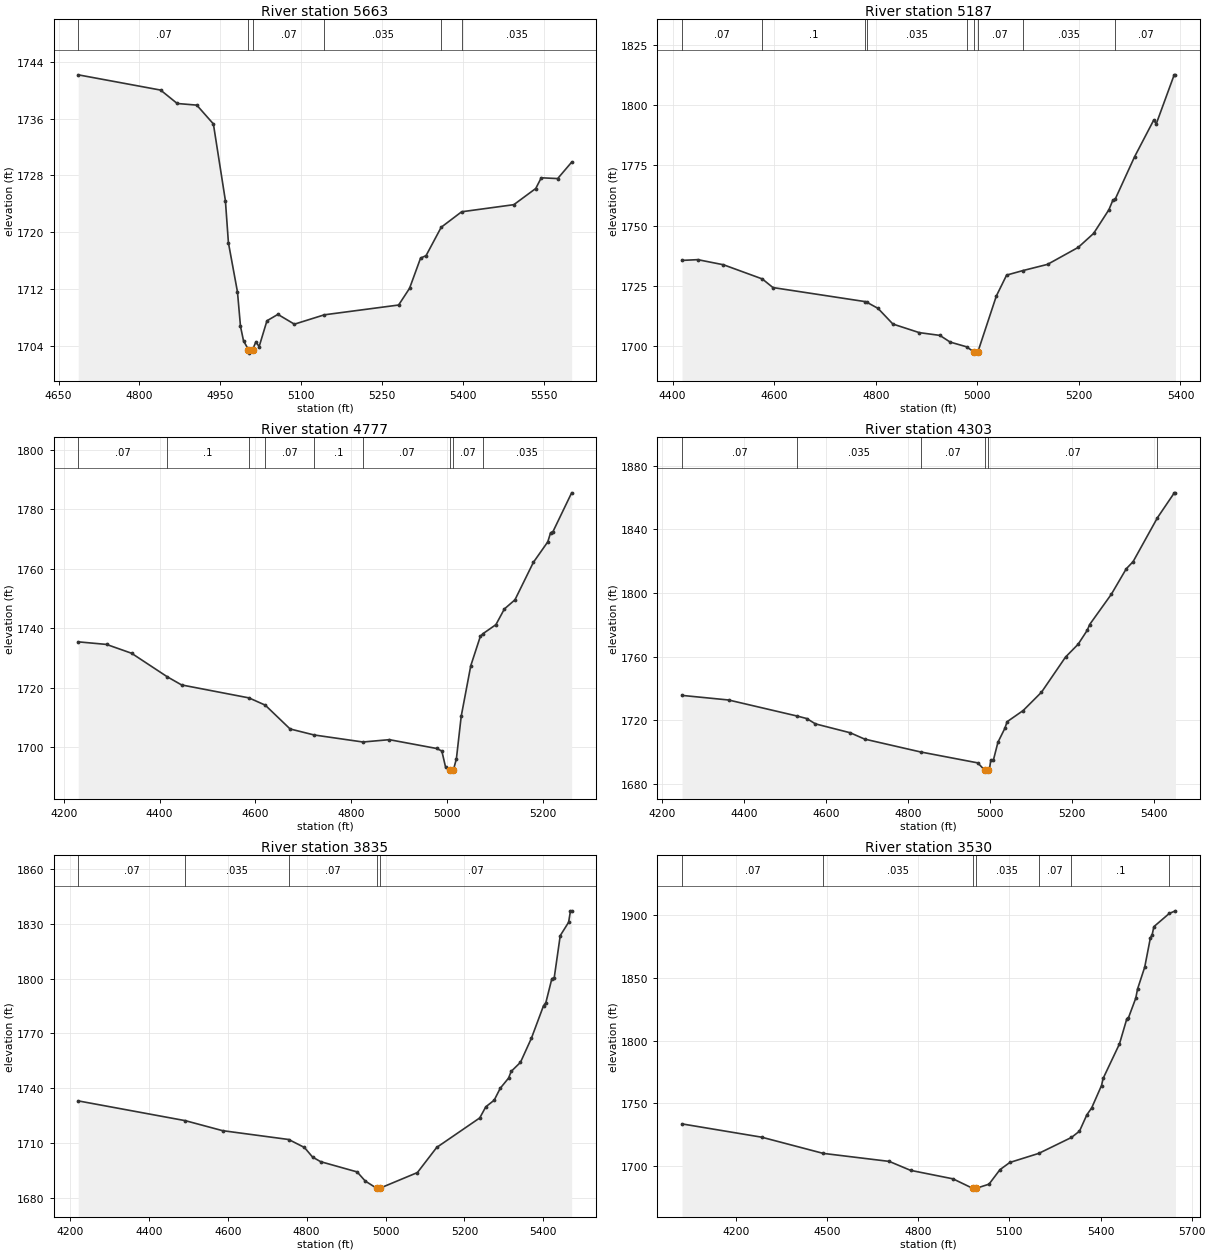
Type RM Length L Ch R = 1,5663,476,476,476
BEGIN DESCRIPTION:
Stream0030 12.0
END DESCRIPTION:
XS GIS Cut Line= 3
      1967401.74     13936436.51      1967125.00     13936575.00
      1966529.60     13936688.03
#Sta/Elev= 30
  4686.3 1742.17  4839.2 1740.02  4870.0 1738.13  4906.3 1737.90  4937.1 1735.25
  4959.4 1724.43  4965.0 1718.50  4981.8 1711.57  4987.4 1706.72  4993.0 1704.69
  5002.1 1703.45  5002.6 1702.95  5009.8 1703.45  5016.1 1704.56  5021.9 1703.85
  5036.5 1707.51  5056.8 1708.41  5087.4 1707.03  5143.0 1708.35  5280.8 1709.73
  5301.1 1712.09  5321.5 1716.34  5331.7 1716.69  5359.8 1720.69  5397.7 1722.87
  5494.5 1723.87  5535.2 1726.15  5545.4 1727.66  5575.9 1727.55  5601.8 1729.86
#Mann=6,-1,0
  4686.3    0.07       0  5002.1    0.05       0  5009.8    0.07       0
  5143.0   0.035       0  5359.8    0.07       0  5397.7   0.035       0
Bank Sta=5002.1,5009.8
Exp/Cntr=0.3,0.1

Type RM Length L Ch R = 1,5187,410,410,410
BEGIN DESCRIPTION:
Stream0030 11.0
END DESCRIPTION:
XS GIS Cut Line= 3
      1967285.49     13936279.88      1966725.00     13936375.00
      1966325.02     13936425.00
#Sta/Elev= 30
  4418.6 1735.60  4449.5 1735.91  4500.2 1733.79  4576.6 1727.91  4597.6 1724.33
  4778.2 1718.53  4783.2 1718.15  4804.5 1715.69  4833.8 1709.19  4885.7 1705.63
  4926.3 1704.48  4946.5 1701.71  4978.8 1699.75  4993.3 1697.62  4993.8 1697.12
  5001.1 1697.62  5037.5 1720.83  5057.7 1729.50  5089.5 1731.36  5138.3 1733.95
  5198.7 1741.00  5229.0 1746.79  5259.2 1756.65  5266.8 1760.52  5271.6 1761.05
  5309.6 1778.57  5347.4 1793.83  5352.4 1792.28  5387.7 1812.61  5390.2 1812.61
#Mann=9,-1,0
  4418.6    0.07       0  4576.6     0.1       0  4778.2    0.07       0
  4783.2   0.035       0  4978.8    0.07       0  4993.3    0.05       0
  5001.1    0.07       0  5089.5   0.035       0  5271.6    0.07       0
Bank Sta=4993.3,5001.1
Exp/Cntr=0.3,0.1

Type RM Length L Ch R = 1,4777,474,474,474
BEGIN DESCRIPTION:
Stream0030 10.0
END DESCRIPTION:
XS GIS Cut Line= 4
      1967311.60     13936249.64      1966575.00     13936025.00
      1966475.00     13936025.00      1966315.61     13936045.51
#Sta/Elev= 30
  4229.8 1735.45  4289.0 1734.58  4341.2 1731.62  4416.3 1723.67  4445.8 1720.98
  4586.5 1716.63  4620.5 1714.20  4672.4 1706.20  4722.6 1704.18  4824.6 1701.82
  4879.8 1702.60  4978.3 1699.65  4989.4 1698.81  4997.3 1693.35  5006.0 1692.54
  5006.5 1692.04  5013.8 1692.54  5019.9 1696.24  5029.9 1710.45  5049.9 1727.44
  5069.9 1737.29  5075.5 1738.20  5102.4 1741.22  5120.1 1746.49  5142.2 1749.56
  5180.6 1762.12  5210.8 1769.03  5216.6 1772.06  5221.7 1772.49  5260.6 1785.48
#Mann=9,-1,0
  4229.8    0.07       0  4416.3     0.1       0  4586.5   0.035       0
  4620.5    0.07       0  4722.6     0.1       0  4824.6    0.07       0
  5006.0    0.05       0  5013.8    0.07       0  5075.5   0.035       0
Bank Sta=5006,5013.8
Exp/Cntr=0.3,0.1

Type RM Length L Ch R = 1,4303,468,468,468
BEGIN DESCRIPTION:
Stream0030 9.0
END DESCRIPTION:
XS GIS Cut Line= 3
      1967342.08     13936228.12      1966825.00     13935675.00
      1966624.99     13935274.99
#Sta/Elev= 30
  4247.8 1735.56  4361.4 1732.67  4529.4 1722.54  4552.4 1720.99  4573.4 1717.65
  4658.4 1712.06  4693.6 1708.07  4830.0 1700.00  4969.6 1693.13  4986.9 1688.44
  4987.4 1687.94  4995.1 1688.44  4997.9 1688.81  5001.5 1694.89  5007.8 1694.89
  5018.9 1706.12  5035.7 1714.82  5041.3 1719.02  5080.4 1726.03  5125.2 1737.57
  5183.9 1759.67  5214.6 1767.73  5237.0 1776.57  5242.6 1780.07  5295.7 1799.17
  5332.0 1815.14  5348.8 1819.68  5408.3 1847.32  5449.4 1862.94  5452.2 1862.94
#Mann=6,-1,0
  4247.8    0.07       0  4529.4   0.035       0  4830.0    0.07       0
  4986.9    0.05       0  4995.1    0.07       0  5408.3     0.1       0
Bank Sta=4986.9,4995.1
Exp/Cntr=0.3,0.1

Type RM Length L Ch R = 1,3835,305,305,305
BEGIN DESCRIPTION:
Stream0030 8.0
END DESCRIPTION:
XS GIS Cut Line= 3
      1967355.54     13936132.79      1967175.00     13935375.00
      1966775.00     13935125.00
#Sta/Elev= 30
  4221.0 1733.06  4492.5 1722.24  4586.9 1716.77  4754.6 1711.93  4794.4 1707.57
  4815.0 1702.33  4835.5 1699.80  4928.0 1694.19  4948.6 1689.20  4977.4 1685.28
  4977.9 1684.78  4985.6 1685.28  5080.8 1693.85  5129.7 1707.60  5238.8 1723.74
  5254.1 1729.81  5275.4 1733.44  5290.7 1739.96  5311.9 1745.55  5318.4 1749.17
  5342.0 1754.16  5369.7 1767.33  5400.4 1785.10  5406.3 1786.77  5421.6 1799.97
  5427.5 1800.32  5442.8 1823.47  5464.0 1830.79  5468.8 1837.05  5471.7 1837.05
#Mann=5,-1,0
  4221.0    0.07       0  4492.5   0.035       0  4754.6    0.07       0
  4977.4    0.05       0  4985.6    0.07       0
Bank Sta=4977.4,4985.6
Exp/Cntr=0.3,0.1

Type RM Length L Ch R = 1,3530,655,655,655
BEGIN DESCRIPTION:
Stream0030 7.0
END DESCRIPTION:
XS GIS Cut Line= 3
      1967394.54     13936137.34      1967390.56     13935153.32
      1967150.97     13934559.13
#Sta/Elev= 30
  4022.0 1733.65  4284.3 1723.07  4486.5 1710.20  4704.3 1703.80  4774.3 1696.69
  4914.3 1689.91  4980.2 1682.23  4980.7 1681.73  4988.5 1682.23  5032.7 1685.67
  5068.9 1697.25  5101.3 1702.95  5196.8 1710.20  5304.2 1722.86  5330.7 1727.88
  5354.9 1740.87  5370.8 1746.37  5403.2 1764.20  5408.6 1769.90  5462.3 1797.33
  5486.4 1817.21  5491.8 1818.04  5516.0 1833.75  5521.8 1840.99  5545.5 1858.49
  5564.3 1881.94  5569.7 1883.97  5575.7 1890.68  5626.4 1901.19  5646.7 1903.27
#Mann=7,-1,0
  4022.0    0.07       0  4486.5   0.035       0  4980.2   0.035       0
  4988.5   0.035       0  5196.8    0.07       0  5304.2     0.1       0
  5626.4    0.07       0
Bank Sta=4980.2,4988.5
Exp/Cntr=0.3,0.1

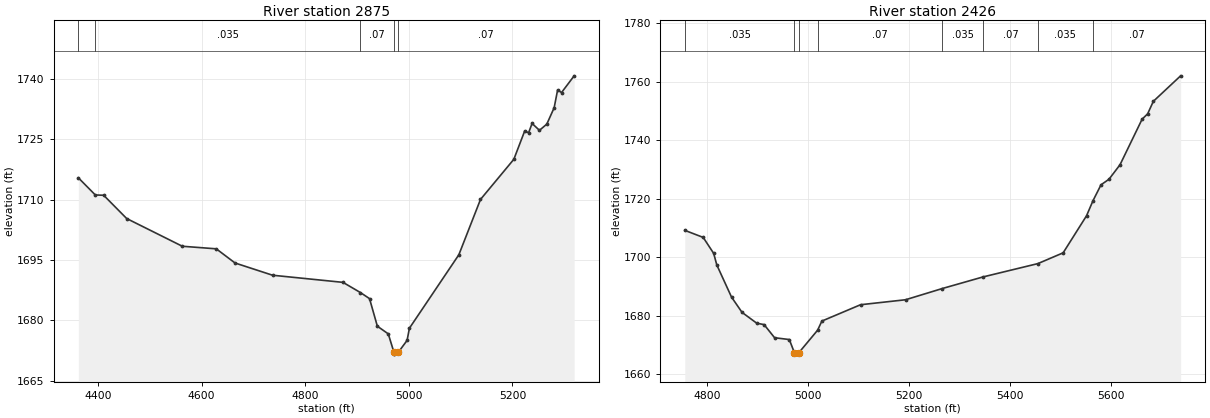
Type RM Length L Ch R = 1,2875,449,449,449
BEGIN DESCRIPTION:
Stream0030 6.0
END DESCRIPTION:
XS GIS Cut Line= 3
      1968325.18     13935513.23      1967975.00     13934975.00
      1967765.82     13934739.51
#Sta/Elev= 30
  4362.1 1715.43  4394.9 1711.16  4411.0 1711.09  4455.4 1705.31  4562.8 1698.42
  4628.4 1697.78  4664.6 1694.26  4737.1 1691.22  4873.0 1689.45  4906.7 1686.91
  4924.2 1685.41  4939.3 1678.56  4960.4 1676.65  4971.2 1672.12  4971.7 1671.62
  4980.0 1672.12  4996.7 1675.03  5001.2 1678.06  5096.6 1696.30  5138.4 1710.05
  5202.8 1720.03  5223.7 1727.05  5231.3 1726.62  5238.0 1728.93  5252.2 1727.22
  5266.4 1728.76  5280.6 1732.84  5287.3 1737.27  5294.8 1736.60  5319.2 1740.76
#Mann=5,-1,0
  4362.1    0.07       0  4394.9   0.035       0  4906.7    0.07       0
  4971.2    0.05       0  4980.0    0.07       0
Bank Sta=4971.2,4980
Exp/Cntr=0.3,0.1

Type RM Length L Ch R = 1,2426,469,469,469
BEGIN DESCRIPTION:
Stream0030 5.0
END DESCRIPTION:
XS GIS Cut Line= 3
      1968575.00     13934975.00      1968375.00     13934825.00
      1968075.89     13934155.26
#Sta/Elev= 30
  4755.0 1709.20  4791.5 1706.78  4812.3 1701.31  4818.5 1697.35  4847.7 1686.36
  4868.5 1681.14  4897.7 1677.43  4912.3 1676.95  4933.1 1672.46  4962.3 1671.84
  4972.4 1667.35  4972.9 1666.85  4981.3 1667.35  5018.4 1675.03  5026.9 1678.16
  5103.6 1683.75  5192.8 1685.45  5265.9 1689.30  5346.1 1693.24  5455.4 1697.82
  5505.5 1701.51  5551.9 1714.19  5564.6 1719.31  5580.6 1724.78  5596.4 1726.68
  5618.3 1731.64  5662.1 1747.23  5673.1 1749.06  5684.4 1753.34  5738.5 1762.06
#Mann=8,-1,0
  4755.0   0.035       0  4972.4   0.035       0  4981.3   0.035       0
  5018.4    0.07       0  5265.9   0.035       0  5346.1    0.07       0
  5455.4   0.035       0  5564.6    0.07       0
Bank Sta=4972.4,4981.3
Exp/Cntr=0.3,0.1