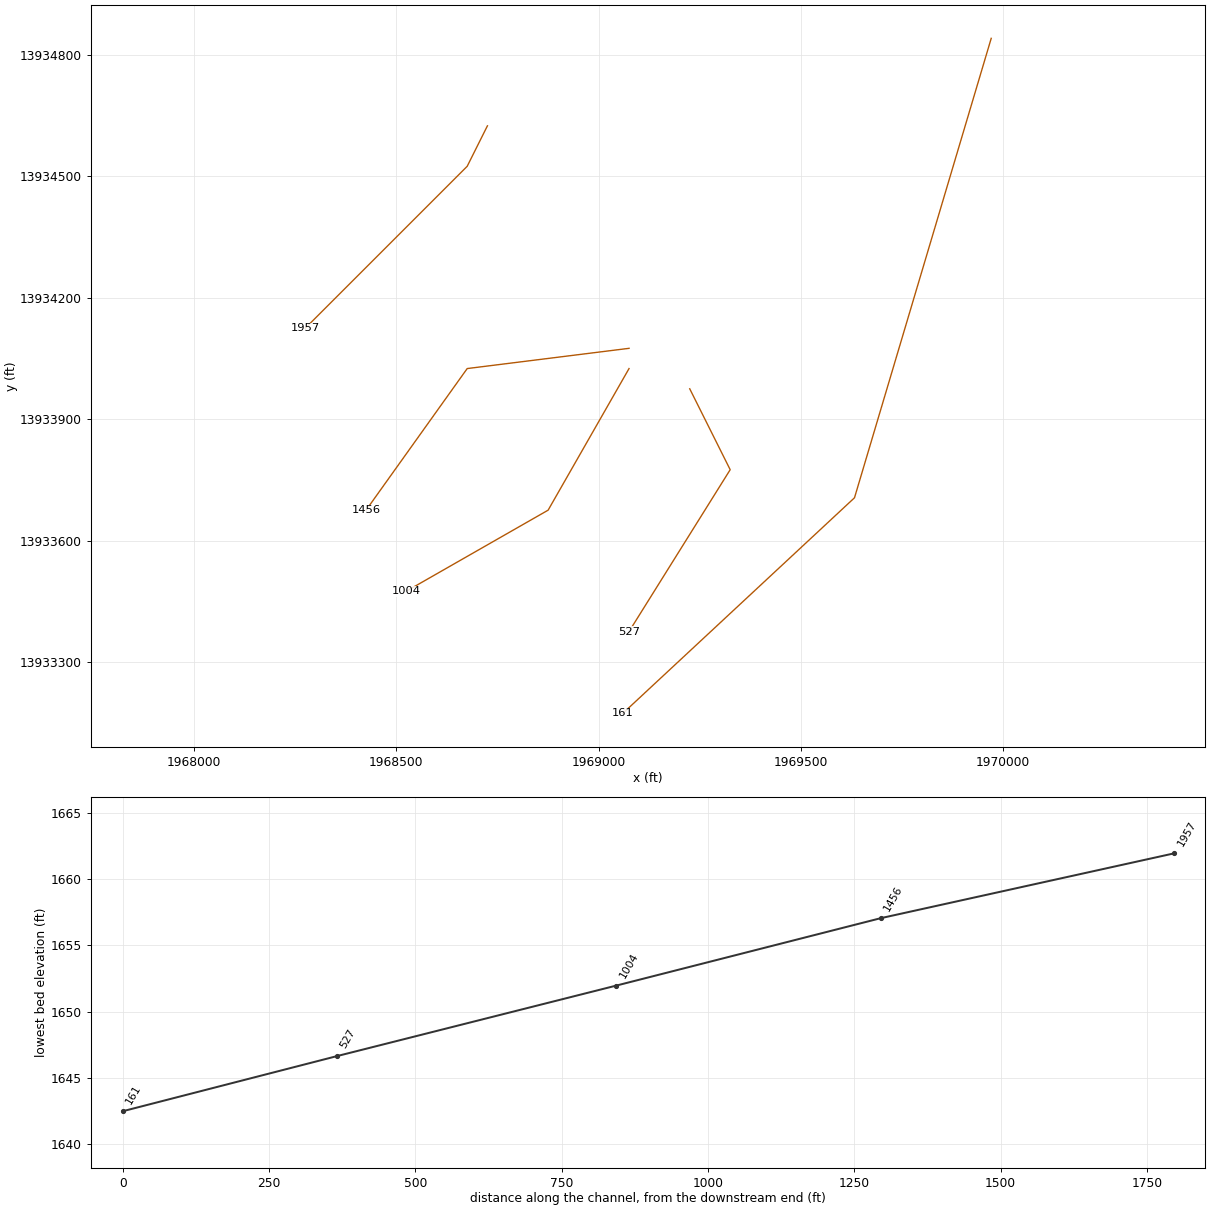
HEC-RAS study Stream0030.prj: Stream0030 Base Level Engineering

--- Stream0030.g01 (geometry) --- (continued)

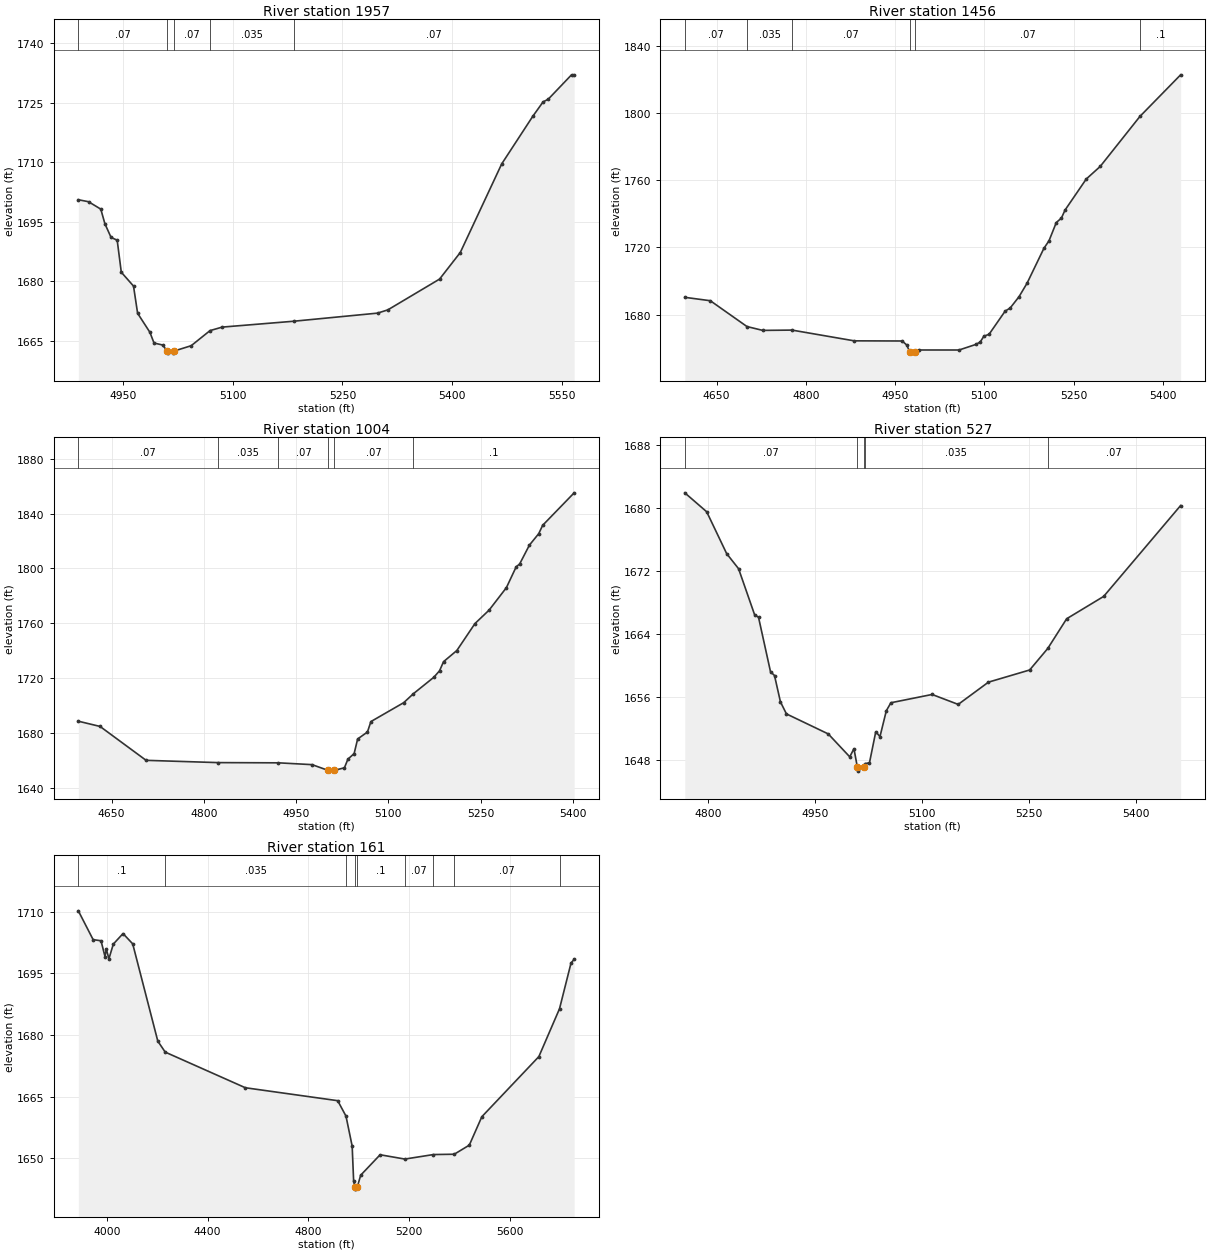
Type RM Length L Ch R = 1,1957,501,501,501
BEGIN DESCRIPTION:
Stream0030 4.0
END DESCRIPTION:
XS GIS Cut Line= 3
      1968724.99     13934624.97      1968675.00     13934525.00
      1968274.97     13934124.97
#Sta/Elev= 30
  4889.1 1700.60  4903.0 1700.10  4919.8 1698.23  4925.4 1694.55  4933.8 1691.11
  4942.2 1690.40  4947.8 1682.33  4964.5 1678.84  4970.1 1671.98  4986.9 1667.19
  4992.5 1664.49  5004.4 1663.98  5010.5 1662.44  5011.0 1661.94  5019.0 1661.94
  5019.5 1662.44  5043.3 1663.81  5069.1 1667.62  5085.7 1668.50  5183.5 1669.98
  5297.9 1672.02  5312.0 1672.84  5382.7 1680.60  5411.0 1687.30  5467.6 1709.63
  5510.0 1721.61  5524.1 1725.25  5531.2 1725.94  5563.0 1732.08  5566.6 1732.08
#Mann=5,-1,0
  4889.1    0.07       0  5010.5    0.05       0  5019.5    0.07       0
  5069.1   0.035       0  5183.5    0.07       0
Bank Sta=5010.5,5019.5
Exp/Cntr=0.3,0.1

Type RM Length L Ch R = 1,1456,452,452,452
BEGIN DESCRIPTION:
Stream0030 3.0
END DESCRIPTION:
XS GIS Cut Line= 3
      1969075.03     13934075.00      1968675.00     13934025.00
      1968424.98     13933674.97
#Sta/Elev= 30
  4596.7 1690.29  4639.6 1688.26  4701.2 1672.88  4727.7 1670.59  4776.9 1670.77
  4881.4 1664.37  4962.1 1664.28  4969.6 1661.90  4975.1 1657.55  4975.6 1657.05
  4984.2 1657.55  4989.8 1658.92  5057.6 1658.91  5085.9 1662.23  5093.2 1663.68
  5099.4 1667.17  5108.0 1668.24  5135.0 1682.03  5143.6 1683.95  5158.4 1690.65
  5171.9 1698.69  5200.2 1719.46  5208.8 1723.97  5221.0 1734.81  5229.6 1737.49
  5235.8 1742.29  5271.4 1760.76  5294.8 1768.23  5361.7 1798.08  5430.0 1822.82
#Mann=6,-1,0
  4596.7    0.07       0  4701.2   0.035       0  4776.9    0.07       0
  4975.1    0.05       0  4984.2    0.07       0  5361.7     0.1       0
Bank Sta=4975.1,4984.2
Exp/Cntr=0.3,0.1

Type RM Length L Ch R = 1,1004,477,477,477
BEGIN DESCRIPTION:
Stream0030 2.0
END DESCRIPTION:
XS GIS Cut Line= 3
      1969075.01     13934025.02      1968875.00     13933675.00
      1968524.96     13933474.98
#Sta/Elev= 30
  4596.0 1688.40  4631.3 1684.59  4706.2 1659.84  4823.0 1658.18  4921.4 1658.02
  4976.1 1656.69  5002.5 1652.46  5003.0 1651.96  5011.6 1652.46  5028.7 1654.39
  5034.4 1660.71  5044.5 1664.76  5050.2 1675.44  5066.1 1680.48  5071.8 1688.14
  5125.1 1701.93  5141.0 1708.52  5174.1 1720.47  5183.4 1725.22  5189.9 1731.86
  5211.5 1739.99  5241.0 1759.69  5264.0 1769.51  5292.1 1785.89  5308.0 1801.09
  5313.7 1803.21  5329.5 1816.93  5344.7 1825.32  5351.1 1831.42  5402.3 1855.12
#Mann=6,-1,0
  4596.0    0.07       0  4823.0   0.035       0  4921.4    0.07       0
  5002.5    0.05       0  5011.6    0.07       0  5141.0     0.1       0
Bank Sta=5002.5,5011.6
Exp/Cntr=0.3,0.1

Type RM Length L Ch R = 1,527,366,366,366
BEGIN DESCRIPTION:
Stream0030 1.0
END DESCRIPTION:
XS GIS Cut Line= 3
      1969225.01     13933974.98      1969325.00     13933775.00
      1969074.99     13933374.99
#Sta/Elev= 30
  4767.9 1681.89  4798.6 1679.49  4826.6 1674.19  4843.3 1672.28  4865.7 1666.47
  4871.3 1666.12  4888.1 1659.23  4893.7 1658.75  4902.0 1655.42  4910.4 1653.89
  4969.1 1651.35  4999.2 1648.45  5005.1 1649.48  5009.9 1647.14  5010.4 1646.64
  5019.0 1647.14  5020.3 1647.57  5026.9 1647.71  5035.7 1651.63  5041.6 1651.01
  5050.5 1654.29  5056.9 1655.30  5114.7 1656.35  5151.3 1655.09  5193.7 1657.91
  5251.5 1659.45  5276.9 1662.18  5303.4 1665.94  5355.3 1668.77  5463.2 1680.28
#Mann=5,-1,0
  4767.9    0.07       0  5009.9    0.05       0  5019.0    0.07       0
  5020.3   0.035       0  5276.9    0.07       0
Bank Sta=5009.9,5019
Exp/Cntr=0.3,0.1

Type RM Length L Ch R = 1,161,0,0,0
BEGIN DESCRIPTION:
Stream0030 0.0
END DESCRIPTION:
XS GIS Cut Line= 3
      1969970.21     13934841.23      1969632.28     13933705.62
      1969059.59     13933172.72
#Sta/Elev= 30
  3887.4 1710.26  3946.1 1703.24  3977.4 1702.97  3993.2 1699.12  3998.4 1700.96
  4008.7 1698.57  4026.3 1702.17  4064.7 1704.72  4103.1 1702.22  4202.7 1678.52
  4232.1 1675.85  4550.1 1667.17  4916.4 1664.02  4949.3 1660.26  4973.8 1652.96
  4979.6 1644.46  4984.8 1642.98  4985.3 1642.48  4994.0 1642.98  5007.6 1645.87
  5084.7 1650.85  5182.7 1649.80  5296.3 1650.90  5378.8 1650.98  5438.5 1653.19
  5488.3 1660.12  5714.5 1674.76  5796.4 1686.41  5842.0 1697.52  5854.5 1698.47
#Mann=9,-1,0
  3887.4     0.1       0  4232.1   0.035       0  4949.3     0.1       0
  4984.8    0.05       0  4994.0     0.1       0  5182.7    0.07       0
  5296.3   0.035       0  5378.8    0.07       0  5796.4   0.035       0
Bank Sta=4984.8,4994
Exp/Cntr=0.3,0.1

Chan Stop Cuts=-1