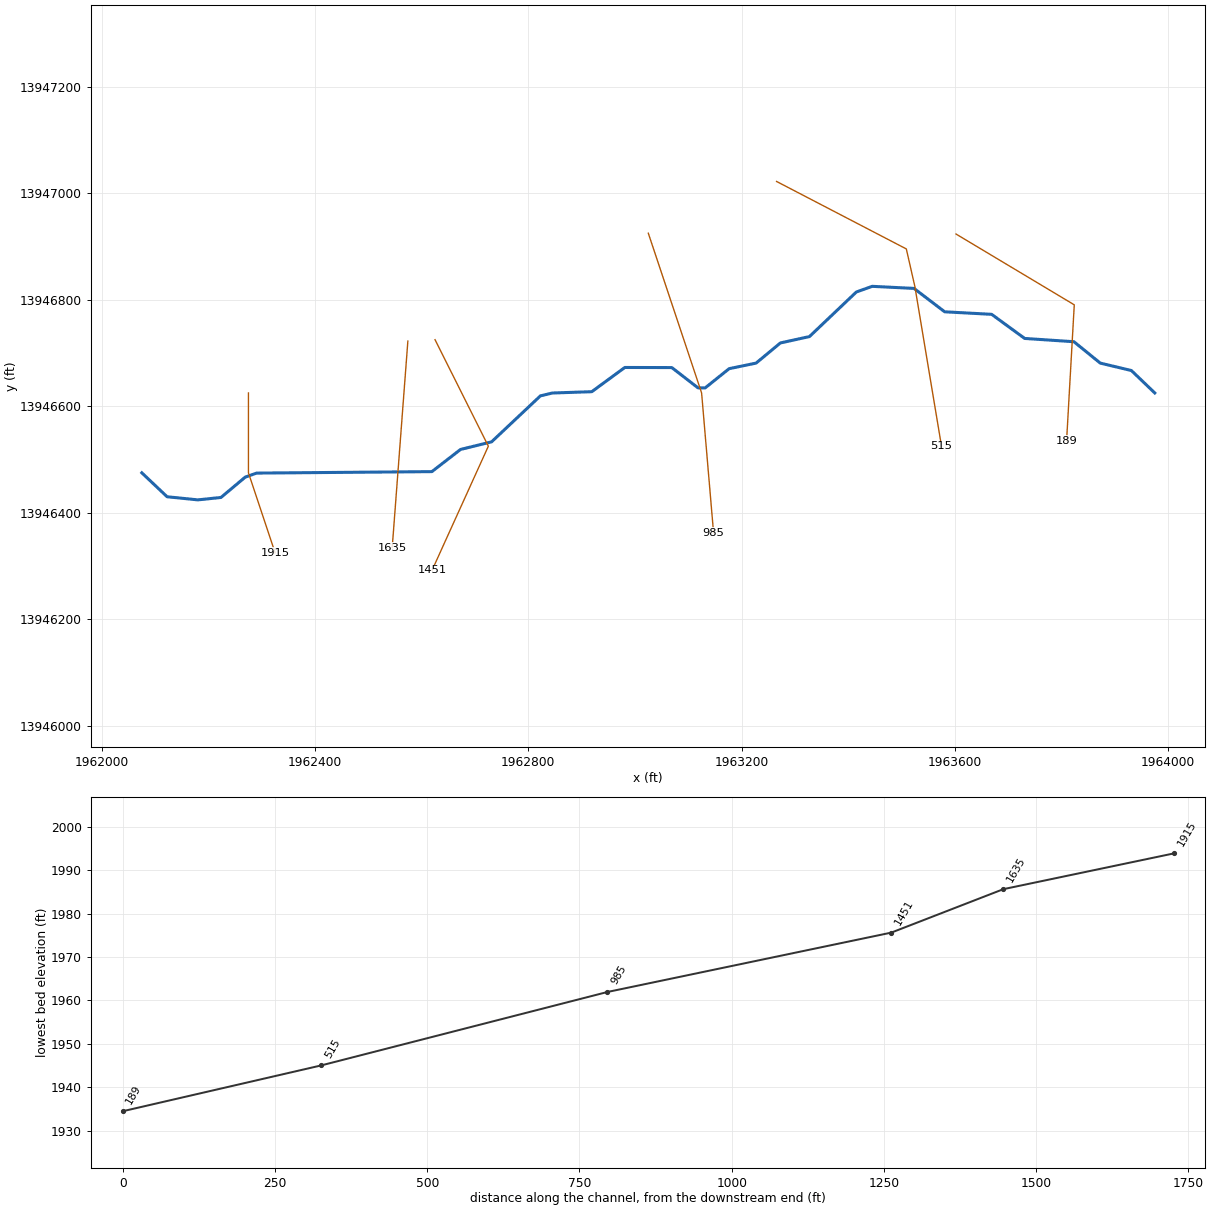
--- Stream0031.prj (project) ---

Proj Title=Stream0031 Base Level Engineering
Current Plan=p01
Default Exp/Contr=0.3,0.1
English Units
Geom File=g01
Flow File=f01
Plan File=p01
BEGIN DESCRIPTION:
Stream0031
END DESCRIPTION:

--- Stream0031.p01 (plan) ---

Plan Title=Multiple Run
Short Identifier=Multiple
Geom File=g01
Flow File=f01
Subcritical Flow
K Sum by GR= 0
Std Step Tol= 0.01
Critical Tol= 0.01
Num of Std Step Trials= 20
Max Error Tol= 0.3
Flow Tol Ratio= 0.001
Split Flow NTrial= 30
Split Flow Tol= 0.02
Split Flow Ratio= 0.02
Log Output Level= 0
Friction Slope Method= 1
Unsteady Friction Slope Method= 2
Unsteady Bridges Friction Slope Method= 1
Parabolic Critical Depth
Global Vel Dist=  1 , 1 , 1
Global Log Level= 0
CheckData=True
Encroach Param= -1, 0, 0, 0
BEGIN DESCRIPTION:
Multiple Run
END DESCRIPTION:

--- Stream0031.f01 (steady flow) ---

Flow Title=Multiple
Number of Profiles=7
Profile Names=10-year,25-year,50-year,1pct_min,100-year,1pct_plu,500-year
River Rch & RM= Stream0031,Reach-1,1915
     315     493     648     415     828    1652    1326
River Rch & RM= Stream0031,Reach-1,1635
     440     705     944     614    1224    2443    2026
Boundary for River Rch & Prof#=Stream0031,Reach-1,1
Up Type=0
Dn Type=3
Dn Slope=0.005
Boundary for River Rch & Prof#=Stream0031,Reach-1,2
Up Type=0
Dn Type=3
Dn Slope=0.005
Boundary for River Rch & Prof#=Stream0031,Reach-1,3
Up Type=0
Dn Type=3
Dn Slope=0.005
Boundary for River Rch & Prof#=Stream0031,Reach-1,4
Up Type=0
Dn Type=3
Dn Slope=0.005
Boundary for River Rch & Prof#=Stream0031,Reach-1,5
Up Type=0
Dn Type=3
Dn Slope=0.005
Boundary for River Rch & Prof#=Stream0031,Reach-1,6
Up Type=0
Dn Type=3
Dn Slope=0.005
Boundary for River Rch & Prof#=Stream0031,Reach-1,7
Up Type=0
Dn Type=3
Dn Slope=0.005

--- Stream0031.g01 (geometry) ---

Geom Title=Existing Conditions

River Reach=Stream0031,Reach-1
Reach XY= 30
      1962075.00     13946475.00      1962122.45     13946430.05
      1962180.06     13946424.19      1962223.41     13946428.70
      1962268.94     13946466.86      1962290.22     13946474.48
      1962619.07     13946477.24      1962672.83     13946518.86
      1962731.05     13946533.16      1962822.58     13946619.46
      1962845.05     13946624.87      1962919.02     13946627.36
      1962980.98     13946672.83      1963069.11     13946672.63
      1963118.40     13946634.44      1963131.62     13946634.42
      1963176.64     13946670.57      1963227.19     13946681.05
      1963272.81     13946718.89      1963327.29     13946730.85
      1963415.22     13946814.54      1963445.05     13946825.21
      1963523.40     13946821.30      1963580.97     13946777.36
      1963669.03     13946772.65      1963730.97     13946727.35
      1963823.42     13946721.18      1963872.78     13946681.03
      1963931.15     13946667.09      1963975.00     13946625.00

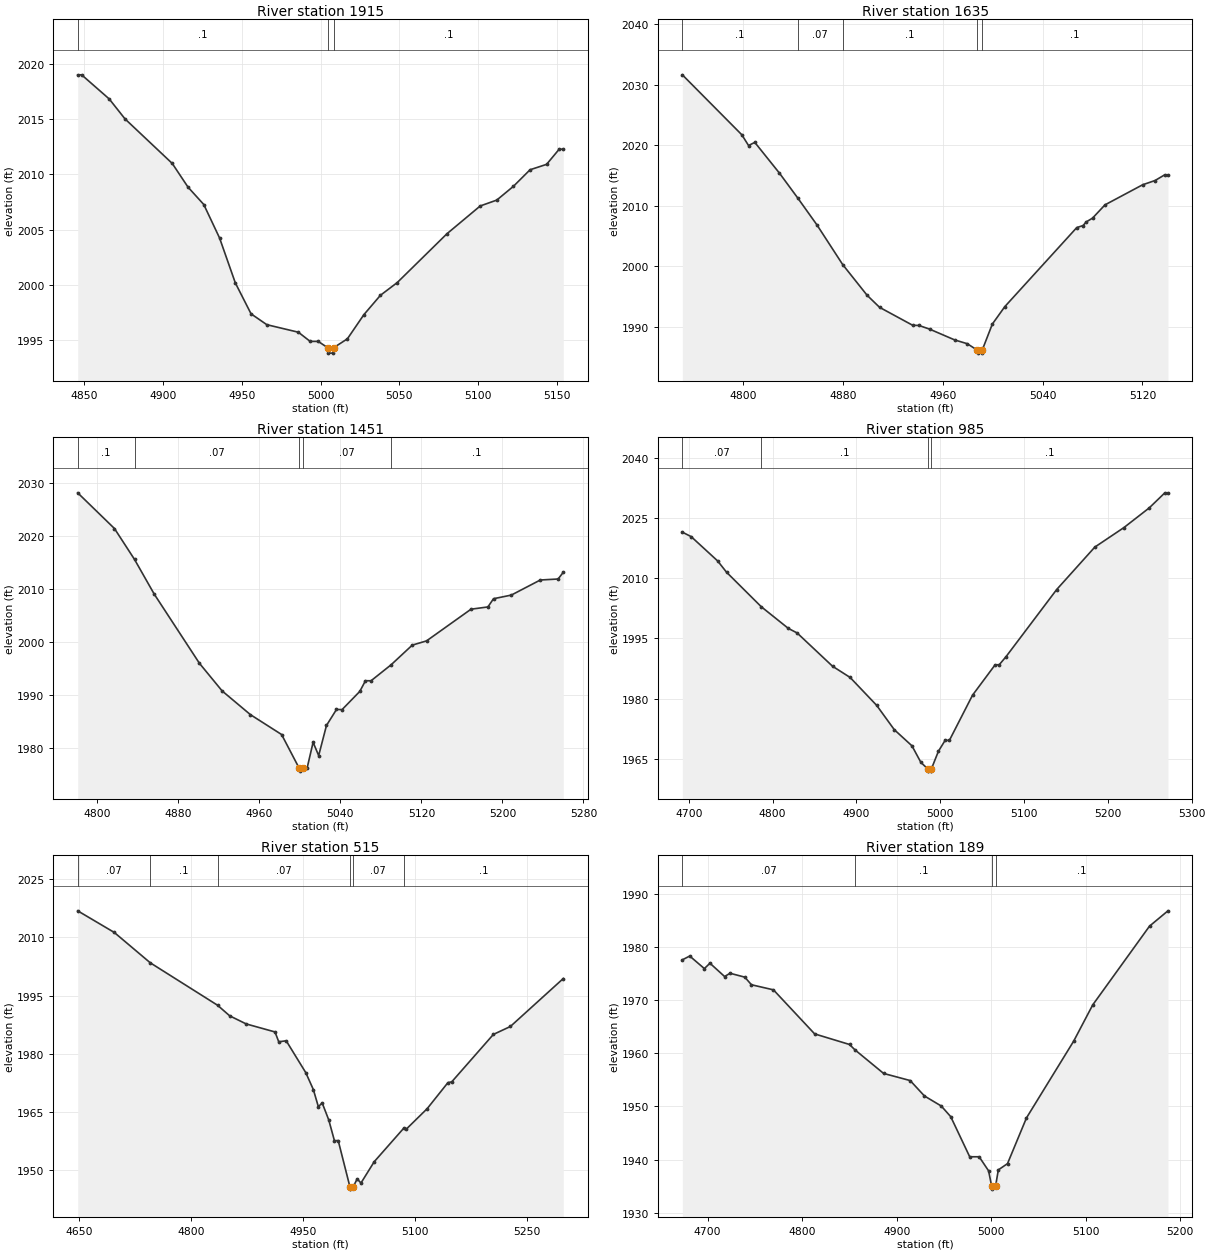
Type RM Length L Ch R = 1,1915,280,280,280
BEGIN DESCRIPTION:
Stream0031 4.0
END DESCRIPTION:
XS GIS Cut Line= 3
      1962275.00     13946624.98      1962275.00     13946475.00
      1962325.00     13946324.99
#Sta/Elev= 30
  4845.9 2019.00  4848.4 2019.00  4865.9 2016.82  4875.9 2015.02  4905.9 2010.99
  4915.9 2008.85  4925.9 2007.28  4935.9 2004.26  4945.9 2000.20  4955.9 1997.40
  4965.9 1996.42  4985.9 1995.74  4993.4 1994.91  4998.5 1994.91  5004.4 1994.35
  5004.7 1993.85  5008.2 1993.85  5008.4 1994.35  5017.0 1995.14  5027.5 1997.33
  5038.0 1999.08  5048.6 2000.22  5080.2 2004.64  5101.3 2007.15  5111.8 2007.68
  5122.4 2008.93  5132.9 2010.42  5143.4 2010.91  5151.4 2012.28  5154.0 2012.28
#Mann=3,-1,0
  4845.9     0.1       0  5004.4    0.05       0  5008.4     0.1       0
Bank Sta=5004.4,5008.4
Exp/Cntr=0.3,0.1

Type RM Length L Ch R = 1,1635,184,184,184
BEGIN DESCRIPTION:
Mapping XS 6c2debda
END DESCRIPTION:
XS GIS Cut Line= 2
      1962574.04     13946722.44      1962544.68     13946334.75
#Sta/Elev= 30
  4751.6 2031.67  4799.2 2021.75  4804.6 2019.97  4809.6 2020.49  4829.3 2015.41
  4843.9 2011.31  4859.4 2006.82  4880.0 2000.26  4899.5 1995.19  4909.5 1993.19
  4936.0 1990.22  4941.0 1990.19  4949.6 1989.58  4969.7 1987.79  4979.7 1987.17
  4987.7 1986.11  4988.0 1985.61  4991.5 1985.61  4991.7 1986.11  4999.8 1990.42
  5009.8 1993.31  5067.4 2006.39  5072.4 2006.72  5075.0 2007.33  5080.0 2007.95
  5090.0 2010.15  5120.1 2013.47  5130.1 2014.18  5137.8 2015.12  5140.4 2015.12
#Mann=5,-1,0
  4751.6     0.1       0  4843.9    0.07       0  4880.0     0.1       0
  4987.7    0.05       0  4991.7     0.1       0
Bank Sta=4987.7,4991.7
Exp/Cntr=0.3,0.1

Type RM Length L Ch R = 1,1451,466,466,466
BEGIN DESCRIPTION:
Stream0031 3.0
END DESCRIPTION:
XS GIS Cut Line= 3
      1962625.00     13946725.01      1962725.00     13946525.00
      1962619.43     13946292.02
#Sta/Elev= 30
  4780.7 2028.21  4817.0 2021.46  4836.8 2015.62  4856.2 2009.08  4900.9 1995.98
  4923.3 1990.76  4951.2 1986.28  4982.0 1982.52  4999.5 1976.10  4999.8 1975.60
  5003.5 1976.10  5007.1 1976.10  5013.1 1981.05  5018.6 1978.54  5026.3 1984.23
  5036.2 1987.26  5041.7 1987.23  5059.2 1990.67  5064.8 1992.69  5070.3 1992.68
  5090.1 1995.70  5111.0 1999.42  5125.1 2000.22  5169.0 2006.21  5185.7 2006.64
  5191.2 2008.19  5208.8 2008.88  5237.4 2011.73  5255.0 2011.92  5260.1 2013.20
#Mann=5,-1,0
  4780.7     0.1       0  4836.8    0.07       0  4999.5    0.05       0
  5003.5    0.07       0  5090.1     0.1       0
Bank Sta=4999.5,5003.5
Exp/Cntr=0.3,0.1

Type RM Length L Ch R = 1,985,470,470,470
BEGIN DESCRIPTION:
Stream0031 2.0
END DESCRIPTION:
XS GIS Cut Line= 3
      1963025.01     13946924.96      1963125.00     13946625.00
      1963147.40     13946362.64
#Sta/Elev= 30
  4692.2 2021.51  4702.7 2020.40  4734.3 2014.34  4744.9 2011.53  4786.4 2002.91
  4818.7 1997.51  4829.2 1996.37  4871.4 1988.08  4892.4 1985.28  4924.1 1978.32
  4945.1 1972.26  4966.2 1968.23  4976.8 1964.12  4985.3 1962.42  4985.6 1961.92
  4989.1 1961.92  4989.3 1962.42  4997.8 1966.88  5005.8 1969.60  5010.9 1969.60
  5038.5 1980.86  5065.4 1988.42  5070.4 1988.46  5078.6 1990.50  5138.9 2007.20
  5184.4 2017.78  5219.2 2022.66  5249.3 2027.55  5268.0 2031.32  5271.7 2031.32
#Mann=4,-1,0
  4692.2    0.07       0  4786.4     0.1       0  4985.3    0.05       0
  4989.3     0.1       0
Bank Sta=4985.3,4989.3
Exp/Cntr=0.3,0.1

Type RM Length L Ch R = 1,515,326,326,326
BEGIN DESCRIPTION:
Stream0031 1.0
END DESCRIPTION:
XS GIS Cut Line= 4
      1963265.64     13947022.16      1963509.00     13946895.44
      1963525.00     13946825.00      1963574.99     13946525.04
#Sta/Elev= 30
  4648.4 2016.87  4697.4 2011.29  4745.7 2003.44  4835.8 1992.49  4852.1 1989.75
  4874.2 1987.66  4912.8 1985.59  4917.8 1983.05  4927.8 1983.31  4954.0 1975.09
  4964.2 1970.70  4970.9 1966.27  4976.0 1967.27  4984.8 1962.88  4992.4 1957.53
  4997.5 1957.53  5013.3 1945.50  5013.5 1945.00  5017.3 1945.50  5022.9 1947.63
  5028.0 1946.58  5045.7 1952.07  5085.1 1960.69  5088.8 1960.51  5116.7 1965.78
  5144.5 1972.50  5149.6 1972.70  5205.4 1984.95  5228.2 1987.00  5299.1 1999.39
#Mann=6,-1,0
  4648.4    0.07       0  4745.7     0.1       0  4835.8    0.07       0
  5013.3    0.05       0  5017.3    0.07       0  5085.1     0.1       0
Bank Sta=5013.3,5017.3
Exp/Cntr=0.3,0.1

Type RM Length L Ch R = 1,189,0,0,0
BEGIN DESCRIPTION:
Stream0031 0.0
END DESCRIPTION:
XS GIS Cut Line= 3
      1963602.29     13946923.38      1963824.01     13946790.48
      1963809.62     13946535.49
#Sta/Elev= 30
  4673.2 1977.59  4681.0 1978.30  4696.5 1975.94  4702.4 1976.95  4717.9 1974.45
  4723.7 1975.06  4739.3 1974.33  4746.3 1972.90  4769.6 1971.94  4813.2 1963.65
  4850.1 1961.66  4855.8 1960.66  4886.2 1956.21  4914.3 1954.87  4929.4 1951.97
  4947.2 1950.08  4957.2 1948.08  4977.3 1940.53  4987.3 1940.53  4997.3 1937.88
  5000.6 1934.94  5000.9 1934.44  5004.6 1934.94  5007.6 1938.06  5017.3 1939.24
  5037.4 1947.85  5087.4 1962.31  5107.5 1969.11  5167.6 1983.93  5187.1 1986.81
#Mann=4,-1,0
  4673.2    0.07       0  4855.8     0.1       0  5000.6    0.05       0
  5004.6     0.1       0
Bank Sta=5000.6,5004.6
Exp/Cntr=0.3,0.1

Chan Stop Cuts=-1