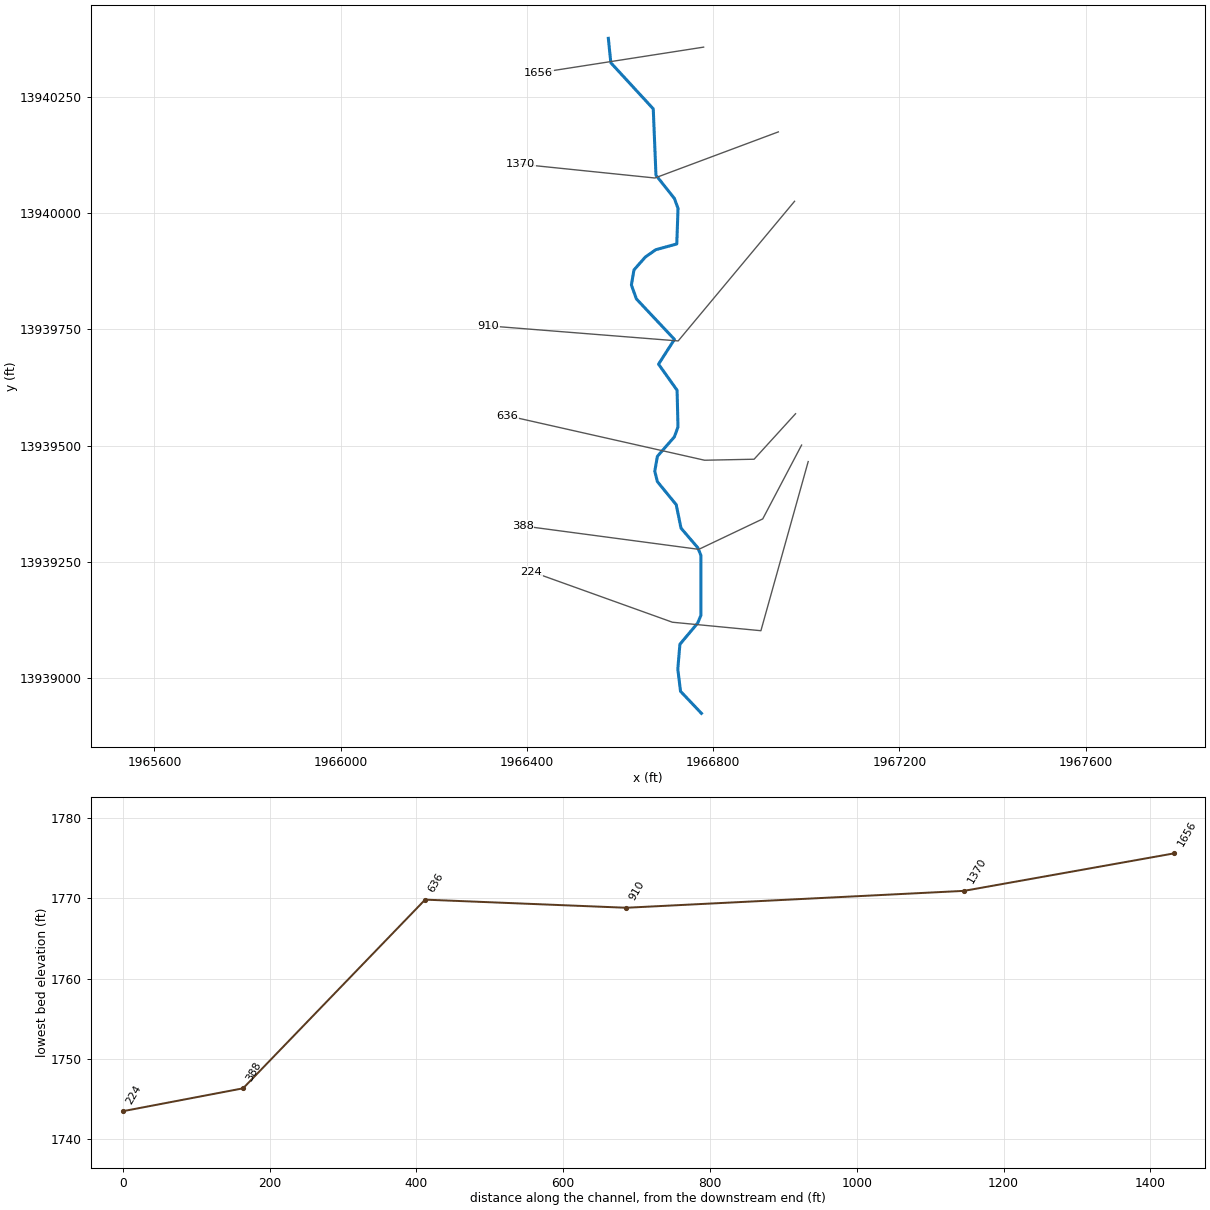
--- Stream0032.prj (project) ---

Proj Title=Stream0032 Base Level Engineering
Current Plan=p01
Default Exp/Contr=0.3,0.1
English Units
Geom File=g01
Flow File=f01
Plan File=p01
BEGIN DESCRIPTION:
Stream0032
END DESCRIPTION:

--- Stream0032.p01 (plan) ---

Plan Title=Multiple Run
Short Identifier=Multiple
Geom File=g01
Flow File=f01
Subcritical Flow
K Sum by GR= 0
Std Step Tol= 0.01
Critical Tol= 0.01
Num of Std Step Trials= 20
Max Error Tol= 0.3
Flow Tol Ratio= 0.001
Split Flow NTrial= 30
Split Flow Tol= 0.02
Split Flow Ratio= 0.02
Log Output Level= 0
Friction Slope Method= 1
Unsteady Friction Slope Method= 2
Unsteady Bridges Friction Slope Method= 1
Parabolic Critical Depth
Global Vel Dist=  1 , 1 , 1
Global Log Level= 0
CheckData=True
Encroach Param= -1, 0, 0, 0
BEGIN DESCRIPTION:
Multiple Run
END DESCRIPTION:

--- Stream0032.f01 (steady flow) ---

Flow Title=Multiple
Number of Profiles=7
Profile Names=10-year,25-year,50-year,1pct_min,100-year,1pct_plu,500-year
River Rch & RM= Stream0032,Reach-1,1656
     600     984    1338     884    1764    3519    3015
Boundary for River Rch & Prof#=Stream0032,Reach-1,1
Up Type=0
Dn Type=3
Dn Slope=0.005
Boundary for River Rch & Prof#=Stream0032,Reach-1,2
Up Type=0
Dn Type=3
Dn Slope=0.005
Boundary for River Rch & Prof#=Stream0032,Reach-1,3
Up Type=0
Dn Type=3
Dn Slope=0.005
Boundary for River Rch & Prof#=Stream0032,Reach-1,4
Up Type=0
Dn Type=3
Dn Slope=0.005
Boundary for River Rch & Prof#=Stream0032,Reach-1,5
Up Type=0
Dn Type=3
Dn Slope=0.005
Boundary for River Rch & Prof#=Stream0032,Reach-1,6
Up Type=0
Dn Type=3
Dn Slope=0.005
Boundary for River Rch & Prof#=Stream0032,Reach-1,7
Up Type=0
Dn Type=3
Dn Slope=0.005

--- Stream0032.g01 (geometry) ---

Geom Title=Existing Conditions

River Reach=Stream0032,Reach-1
Reach XY= 30
      1966575.00     13940375.00      1966580.33     13940322.49
      1966671.46     13940223.53      1966677.28     13940080.94
      1966716.93     13940030.99      1966724.68     13940009.60
      1966722.00     13939933.35      1966676.82     13939920.93
      1966654.50     13939905.29      1966630.00     13939877.52
      1966624.51     13939845.23      1966635.21     13939815.34
      1966716.99     13939728.33      1966682.81     13939675.10
      1966722.64     13939619.11      1966724.60     13939540.27
      1966716.86     13939518.95      1966680.38     13939477.18
      1966674.71     13939445.17      1966680.34     13939422.80
      1966720.78     13939373.28      1966731.11     13939322.82
      1966766.91     13939281.07      1966773.81     13939264.50
      1966773.79     13939135.51      1966766.86     13939118.94
      1966728.70     13939073.41      1966724.19     13939020.01
      1966730.05     13938972.45      1966775.00     13938925.00

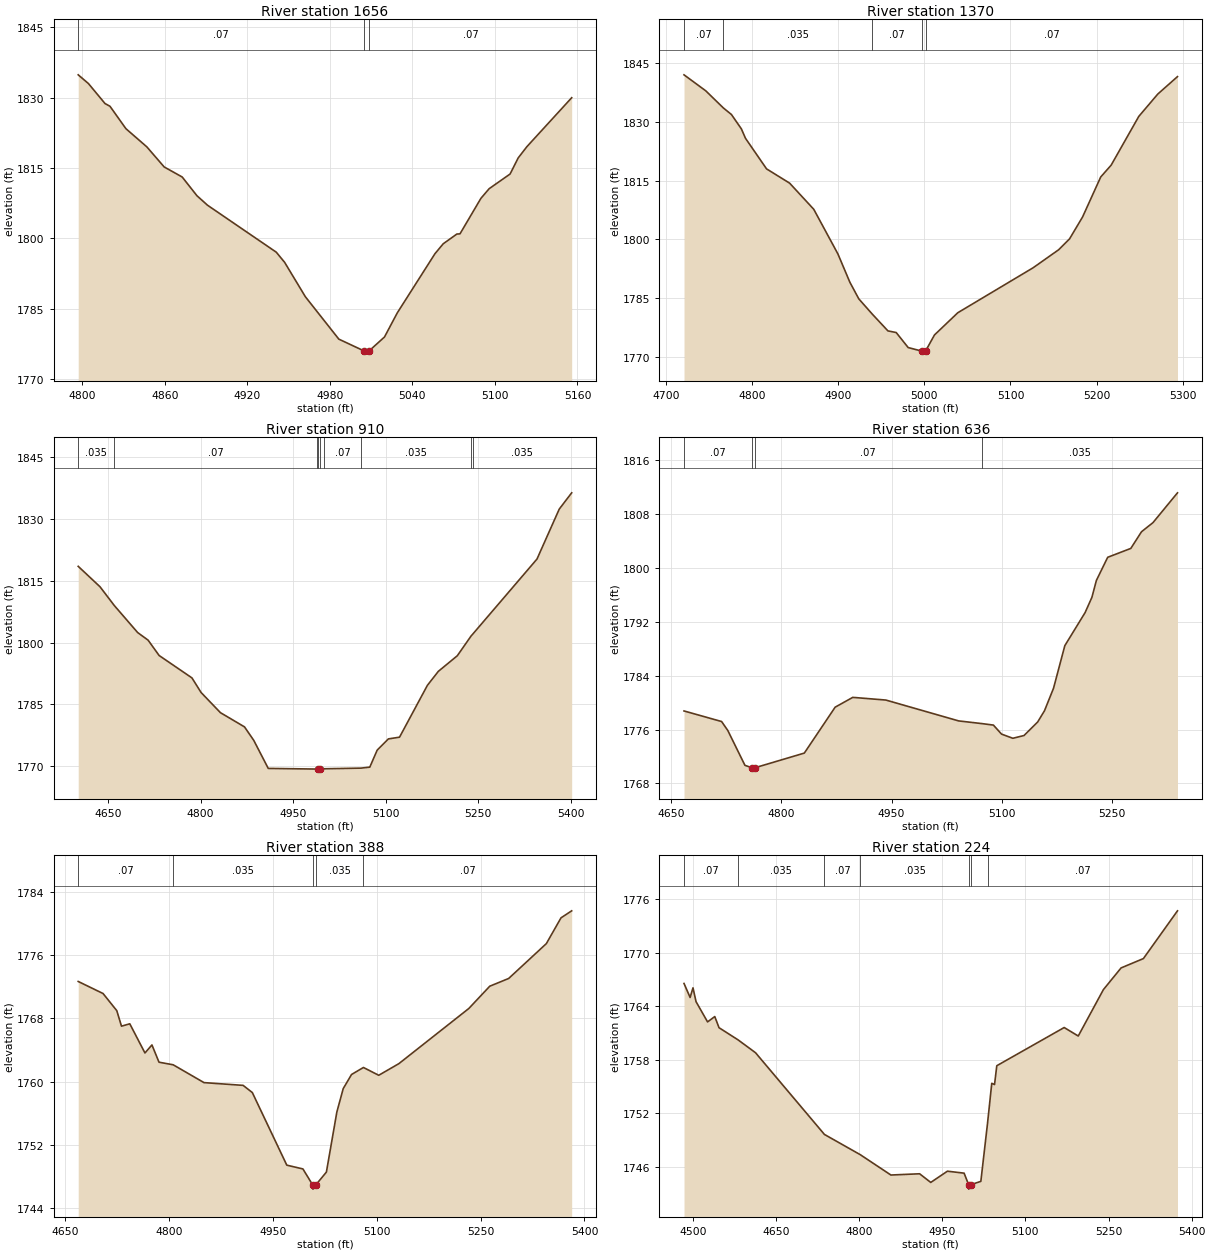
Type RM Length L Ch R = 1,1656,286,286,286
BEGIN DESCRIPTION:
Stream0032 4.0
END DESCRIPTION:
XS GIS Cut Line= 2
      1966779.65     13940356.12      1966425.13     13940300.91
#Sta/Elev= 30
  4797.0 1834.87  4804.4 1833.02  4816.5 1828.75  4820.1 1828.17  4831.7 1823.39
  4846.9 1819.52  4859.5 1815.24  4872.6 1813.10  4883.3 1809.12  4891.0 1807.09
  4941.0 1797.08  4947.1 1794.91  4962.2 1787.57  4986.5 1778.55  5004.6 1776.07
  5004.9 1775.57  5008.4 1775.57  5008.6 1776.07  5019.7 1779.01  5029.0 1784.15
  5056.4 1796.76  5062.4 1798.87  5072.3 1800.94  5074.6 1800.99  5089.8 1808.55
  5095.8 1810.61  5111.0 1813.73  5116.9 1817.16  5123.2 1819.55  5155.8 1829.99
#Mann=3,-1,0
  4797.0    0.07       0  5004.6    0.05       0  5008.6    0.07       0
Bank Sta=5004.6,5008.6
Exp/Cntr=0.3,0.1

Type RM Length L Ch R = 1,1370,460,460,460
BEGIN DESCRIPTION:
Stream0032 3.0
END DESCRIPTION:
XS GIS Cut Line= 3
      1966940.12     13940174.04      1966675.00     13940075.00
      1966386.73     13940104.62
#Sta/Elev= 30
  4721.1 1842.02  4746.4 1837.92  4766.8 1833.55  4776.1 1831.89  4787.7 1828.20
  4792.4 1825.82  4816.9 1817.99  4843.7 1814.34  4871.7 1807.66  4899.7 1796.27
  4913.6 1789.03  4924.0 1784.77  4939.5 1780.91  4957.8 1776.59  4967.4 1776.17
  4981.3 1772.33  4997.4 1771.41  4997.7 1770.91  5001.4 1771.41  5011.8 1775.55
  5038.9 1781.23  5126.4 1792.73  5156.0 1797.33  5168.6 1800.10  5183.7 1805.69
  5204.8 1815.92  5216.9 1818.94  5249.0 1831.40  5271.1 1837.12  5293.9 1841.56
#Mann=5,-1,0
  4721.1    0.07       0  4766.8   0.035       0  4939.5    0.07       0
  4997.4    0.05       0  5001.4    0.07       0
Bank Sta=4997.4,5001.4
Exp/Cntr=0.3,0.1

Type RM Length L Ch R = 1,910,274,274,274
BEGIN DESCRIPTION:
Stream0032 2.0
END DESCRIPTION:
XS GIS Cut Line= 3
      1966975.01     13940025.01      1966725.00     13939725.00
      1966317.32     13939757.39
#Sta/Elev= 30
  4601.8 1818.51  4637.2 1813.54  4660.2 1809.01  4698.1 1802.44  4715.0 1800.60
  4732.9 1796.87  4786.1 1791.43  4800.9 1787.89  4832.2 1783.00  4871.2 1779.55
  4886.2 1776.28  4909.7 1769.47  4988.3 1769.31  4990.3 1769.31  4990.5 1768.81
  4994.3 1769.31  4999.6 1769.38  5060.0 1769.54  5074.2 1769.78  5086.2 1773.91
  5104.3 1776.63  5122.4 1777.05  5167.5 1789.62  5185.3 1793.03  5216.0 1796.81
  5238.3 1801.60  5240.9 1802.04  5345.1 1820.28  5381.2 1832.41  5401.3 1836.35
#Mann=9,-1,0
  4601.8   0.035       0  4660.2    0.07       0  4988.3   0.035       0
  4990.3    0.05       0  4994.3   0.035       0  4999.6    0.07       0
  5060.0   0.035       0  5238.3    0.07       0  5240.9   0.035       0
Bank Sta=4990.3,4994.3
Exp/Cntr=0.3,0.1

Type RM Length L Ch R = 1,636,248,248,248
BEGIN DESCRIPTION:
Stream0032 1.1
END DESCRIPTION:
XS GIS Cut Line= 4
      1966977.09     13939568.62      1966888.08     13939470.93
      1966781.74     13939468.76      1966358.60     13939564.24
#Sta/Elev= 30
  4667.3 1778.76  4718.5 1777.19  4727.0 1775.85  4750.3 1770.68  4759.9 1770.32
  4760.1 1769.82  4763.6 1769.82  4763.9 1770.32  4831.2 1772.50  4873.2 1779.32
  4897.2 1780.78  4942.3 1780.38  5041.5 1777.28  5072.6 1776.89  5088.8 1776.66
  5099.9 1775.32  5115.3 1774.70  5130.5 1775.11  5149.1 1777.12  5158.4 1778.79
  5170.7 1782.13  5186.1 1788.46  5213.7 1793.37  5223.0 1795.64  5229.1 1798.15
  5244.5 1801.59  5276.0 1802.91  5290.6 1805.39  5306.2 1806.74  5339.6 1811.17
#Mann=4,-1,0
  4667.3    0.07       0  4759.9    0.05       0  4763.9    0.07       0
  5072.6   0.035       0
Bank Sta=4759.9,4763.9
Exp/Cntr=0.3,0.1

Type RM Length L Ch R = 1,388,164,164,164
BEGIN DESCRIPTION:
Stream0032 1.0
END DESCRIPTION:
XS GIS Cut Line= 4
      1966990.07     13939501.31      1966906.65     13939342.74
      1966769.30     13939277.35      1966391.14     13939327.70
#Sta/Elev= 30
  4668.7 1772.69  4704.6 1771.16  4724.4 1768.99  4731.2 1767.02  4743.2 1767.32
  4765.1 1763.62  4775.2 1764.64  4785.4 1762.45  4805.9 1762.12  4850.4 1759.86
  4906.9 1759.51  4920.2 1758.60  4970.0 1749.39  4993.3 1748.91  5007.6 1746.85
  5007.8 1746.35  5011.6 1746.85  5027.2 1748.51  5042.3 1756.13  5051.5 1759.10
  5063.5 1760.89  5080.7 1761.78  5102.8 1760.79  5131.8 1762.26  5232.9 1769.26
  5263.2 1772.09  5290.5 1773.07  5344.9 1777.49  5366.1 1780.76  5381.5 1781.65
#Mann=5,-1,0
  4668.7    0.07       0  4805.9   0.035       0  5007.6   0.035       0
  5011.6   0.035       0  5080.7    0.07       0
Bank Sta=5007.6,5011.6
Exp/Cntr=0.3,0.1

Type RM Length L Ch R = 1,224,0,0,0
BEGIN DESCRIPTION:
Stream0032 T
END DESCRIPTION:
XS GIS Cut Line= 4
      1967004.28     13939465.89      1966902.70     13939102.56
      1966712.60     13939120.79      1966409.19     13939229.70
#Sta/Elev= 30
  4483.9 1766.55  4494.9 1764.98  4500.1 1766.06  4505.6 1764.51  4526.4 1762.24
  4539.4 1762.84  4547.1 1761.59  4581.4 1760.23  4612.9 1758.79  4737.3 1749.63
  4802.0 1747.36  4857.3 1745.08  4909.1 1745.22  4929.2 1744.25  4959.3 1745.51
  4989.4 1745.29  4997.5 1744.00  4997.7 1743.50  5001.5 1744.00  5019.6 1744.37
  5031.7 1750.89  5039.3 1755.36  5044.3 1755.22  5048.4 1757.33  5170.0 1761.61
  5195.4 1760.66  5240.8 1765.86  5272.7 1768.29  5313.0 1769.34  5374.5 1774.69
#Mann=7,-1,0
  4483.9    0.07       0  4581.4   0.035       0  4737.3    0.07       0
  4802.0   0.035       0  4997.5   0.035       0  5001.5   0.035       0
  5031.7    0.07       0
Bank Sta=4997.5,5001.5
Exp/Cntr=0.3,0.1

Chan Stop Cuts=-1