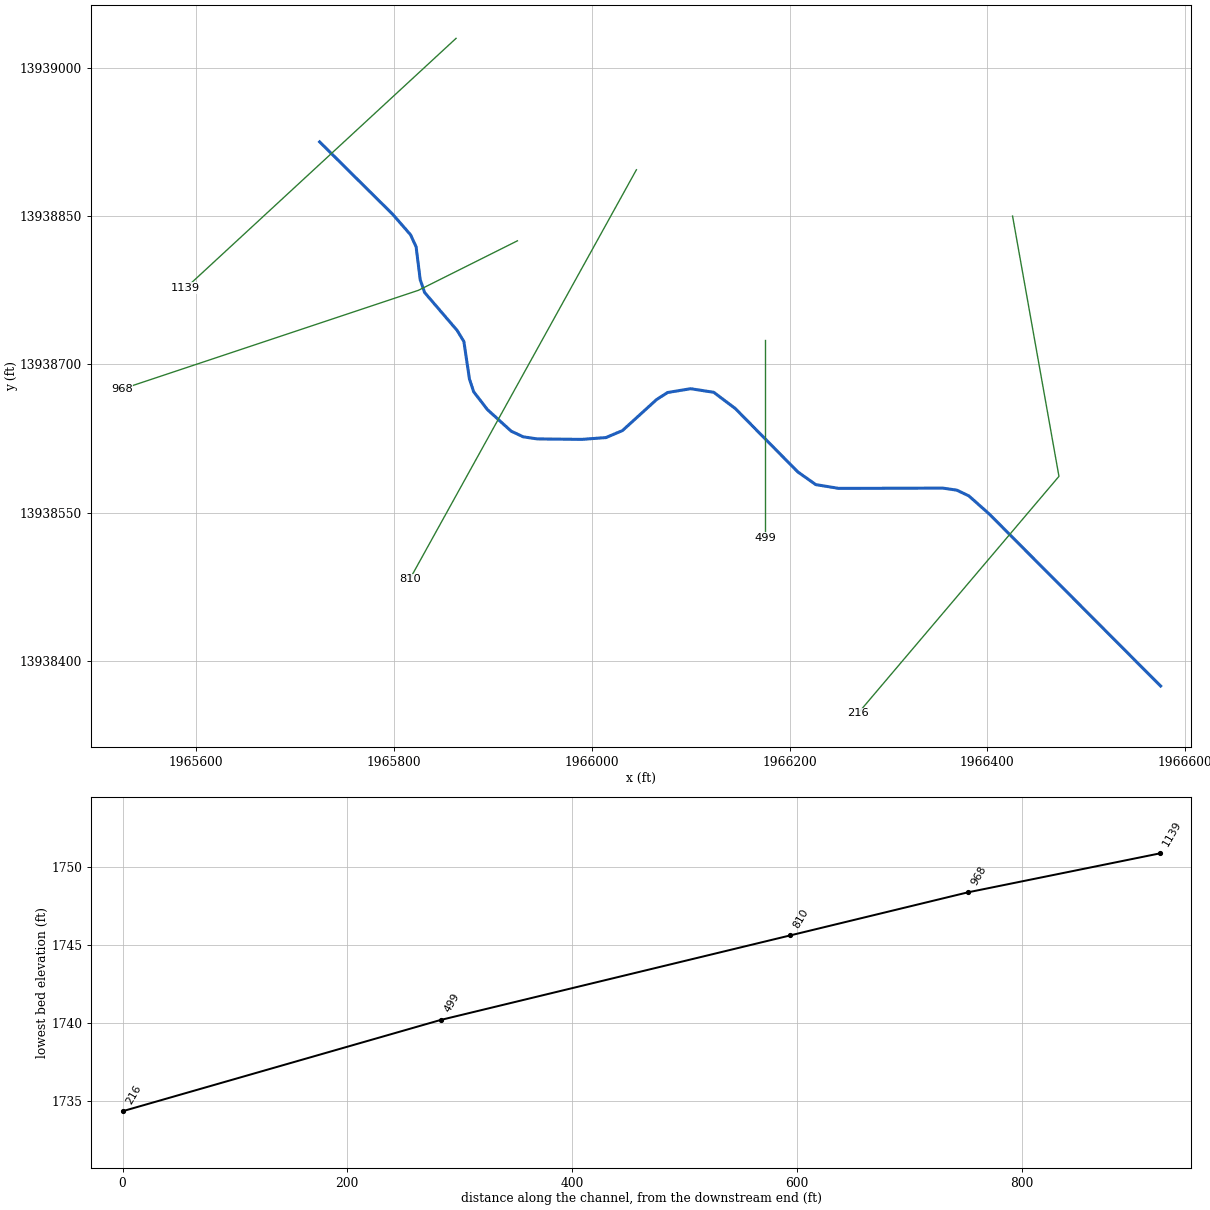
--- Stream0033.prj (project) ---

Proj Title=Stream0033 Base Level Engineering
Current Plan=p01
Default Exp/Contr=0.3,0.1
English Units
Geom File=g01
Flow File=f01
Plan File=p01
Y Axis Title=Elevation
X Axis Title(PF)=Main Channel Distance
X Axis Title(XS)=Station
BEGIN DESCRIPTION:
Stream0033
END DESCRIPTION:
DSS Export Rating Curves= 0
DSS Export Rating Curve Sorted= 0
DSS Export Volume Flow Curves= 0
DXF OffsetX= 0
DXF OffsetY= 0
DXF ScaleX= 1
DXF ScaleY= 10

--- Stream0033.p01 (plan) ---

Plan Title=Multiple Run
Short Identifier=Multiple
Geom File=g01
Flow File=f01
Subcritical Flow
K Sum by GR= 0
Std Step Tol= 0.01
Critical Tol= 0.01
Num of Std Step Trials= 20
Max Error Tol= 0.3
Flow Tol Ratio= 0.001
Split Flow NTrial= 30
Split Flow Tol= 0.02
Split Flow Ratio= 0.02
Log Output Level= 0
Friction Slope Method= 1
Unsteady Friction Slope Method= 2
Unsteady Bridges Friction Slope Method= 1
Parabolic Critical Depth
Global Vel Dist=  1 , 1 , 1
Global Log Level= 0
CheckData=True
Encroach Param= -1, 0, 0, 0
BEGIN DESCRIPTION:
Multiple Run
END DESCRIPTION:

--- Stream0033.f01 (steady flow) ---

Flow Title=Multiple
Program Version=4.10
Number of Profiles= 7
Profile Names=10-year,25-year,50-year,1pct_min,100-year,1pct_plu,500-year
River Rch & RM=Stream0033,Reach-1         ,1139
    1059    1805    2517    1700    3392    6768    6075
Boundary for River Rch & Prof#=Stream0033,Reach-1         , 1
Up Type= 0
Dn Type= 3
Dn Slope=0.008
Boundary for River Rch & Prof#=Stream0033,Reach-1         , 2
Up Type= 0
Dn Type= 3
Dn Slope=0.008
Boundary for River Rch & Prof#=Stream0033,Reach-1         , 3
Up Type= 0
Dn Type= 3
Dn Slope=0.008
Boundary for River Rch & Prof#=Stream0033,Reach-1         , 4
Up Type= 0
Dn Type= 3
Dn Slope=0.008
Boundary for River Rch & Prof#=Stream0033,Reach-1         , 5
Up Type= 0
Dn Type= 3
Dn Slope=0.008
Boundary for River Rch & Prof#=Stream0033,Reach-1         , 6
Up Type= 0
Dn Type= 3
Dn Slope=0.008
Boundary for River Rch & Prof#=Stream0033,Reach-1         , 7
Up Type= 0
Dn Type= 3
Dn Slope=0.008
DSS Import GetInterval= 0
DSS Import GetPeak= 0
DSS Import FillOption= 0

--- Stream0033.g01 (geometry) ---

Geom Title=Existing Conditions
Program Version=4.10

River Reach=Stream0033      ,Reach-1
Reach XY= 30
        1965725.       13938925.       1965798.8     13938851.86
      1965816.91     13938831.08      1965822.52     13938818.97
      1965826.68      13938785.7      1965831.09     13938772.81
       1965863.9     13938734.53       1965870.8     13938723.23
      1965876.43     13938685.45      1965880.72     13938672.41
      1965894.58     13938654.41      1965918.54     13938632.64
      1965930.71     13938626.89      1965944.95     13938624.75
      1965990.04     13938624.27      1966014.45     13938626.12
      1966031.05     13938633.14      1966065.48     13938664.44
      1966076.75     13938671.66      1966100.04     13938675.49
      1966123.36     13938671.86      1966145.07     13938655.53
      1966208.25     13938591.47      1966226.47     13938578.56
      1966249.89     13938574.73      1966355.01     13938575.02
      1966369.14     13938572.93      1966381.19     13938567.18
      1966401.87     13938548.83        1966575.       13938375.

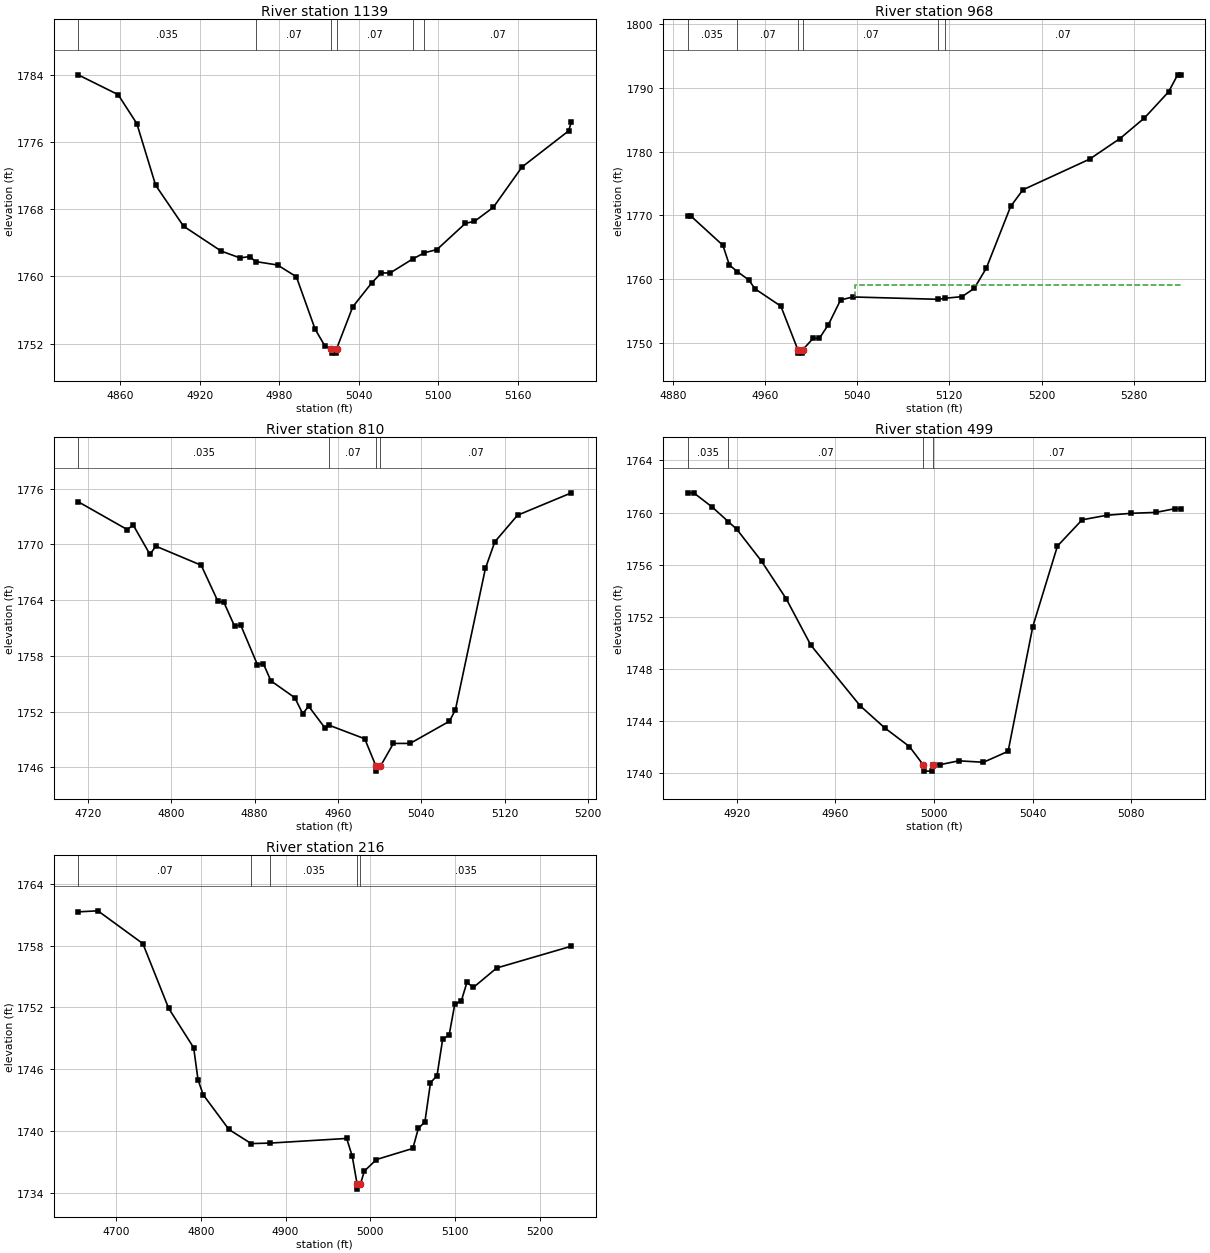
Type RM Length L Ch R = 1 ,1139    ,171,171,171
BEGIN DESCRIPTION:
Stream0033 3.0
END DESCRIPTION:
XS GIS Cut Line= 2
      1965862.92     13939029.63      1965589.75     13938777.27
#Sta/Elev= 30
  4828.4 1784.02  4858.5 1781.66  4872.6 1778.21  4886.8 1770.86  4907.8 1765.99
  4936.2 1763.02  4950.3 1762.21  4957.7 1762.36  4962.2 1761.77  4978.7 1761.36
  4992.9 1759.96    5007 1753.73  5014.4 1751.71  5019.2 1751.36  5019.5 1750.86
    5023 1750.86  5023.2 1751.36  5035.4 1756.37  5049.6 1759.21  5056.9 1760.41
  5063.7 1760.42  5080.5 1762.07  5089.5 1762.82  5098.9  1763.2  5120.4 1766.33
  5127.2 1766.56  5141.4 1768.23    5163 1773.03  5198.1 1777.33  5200.3 1778.39
#Mann= 6 ,-1 , 0
  4828.4    .035       0  4962.2     .07       0  5019.2     .05       0
  5023.2     .07       0  5080.5    .035       0  5089.5     .07       0
Bank Sta=5019.2,5023.2
XS Rating Curve= 0 ,0
Exp/Cntr=0.3,0.1

Type RM Length L Ch R = 1 ,968     ,158,158,158
BEGIN DESCRIPTION:
Stream0033 2.0
END DESCRIPTION:
XS GIS Cut Line= 3
      1965924.96     13938824.98        1965825.       13938775.
      1965524.98     13938674.99
#Sta/Elev= 30
  4892.8 1769.92  4895.5 1769.92  4923.5 1765.29  4929.1  1762.2    4936 1761.16
  4945.9 1759.86  4951.4 1758.45  4973.8 1755.73  4988.6 1748.86  4988.8 1748.36
  4992.3 1748.36  4992.6 1748.86  5001.8 1750.68  5007.2 1750.68  5015.1 1752.85
  5025.6  1756.7  5036.2 1757.18  5110.5 1756.81  5115.9 1756.97    5131 1757.23
  5141.6 1758.53  5152.1 1761.71  5173.2  1771.4  5183.8    1774  5241.7 1778.82
  5268.1 1782.06  5289.2 1785.27  5310.2 1789.38  5318.1 1792.06  5320.8 1792.06
#Mann= 6 ,-1 , 0
  4892.8    .035       0    4936     .07       0  4988.6     .05       0
  4992.6     .07       0  5110.5    .035       0  5115.9     .07       0
#XS Ineff= 2 , 0
                         5038.52         1759.06
Permanent Ineff=
       F       F
Bank Sta=4988.6,4992.6
XS Rating Curve= 0 ,0
Exp/Cntr=0.3,0.1

Type RM Length L Ch R = 1 ,810     ,311,311,311
BEGIN DESCRIPTION:
Stream0033 1.1
END DESCRIPTION:
XS GIS Cut Line= 2
       1966045.2      13938896.8      1965816.06     13938482.78
#Sta/Elev= 30
  4710.8 1774.58  4757.8 1771.59  4763.6 1772.07  4779.6 1768.92  4785.3  1769.8
  4828.8 1767.75  4844.9 1763.85  4850.6 1763.75  4860.9 1761.17  4866.6 1761.34
  4882.7 1757.06  4888.4 1757.17  4895.7 1755.31  4918.6  1753.5  4926.2 1751.78
  4931.9 1752.58  4947.9 1750.19  4951.7 1750.53  4985.7 1749.08  4996.6  1746.1
  4996.8  1745.6  5000.6  1746.1  5013.2 1748.58  5029.2 1748.58    5067 1750.97
  5072.7  1752.2  5101.5 1767.42  5110.5 1770.27  5132.3 1773.13    5184 1775.54
#Mann= 4 ,-1 , 0
  4710.8    .035       0  4951.7     .07       0  4996.6     .05       0
  5000.6     .07       0
Bank Sta=4996.6,5000.6
XS Rating Curve= 0 ,0
Exp/Cntr=0.3,0.1

Type RM Length L Ch R = 1 ,499     ,283,283,283
BEGIN DESCRIPTION:
Stream0033 1.0
END DESCRIPTION:
XS GIS Cut Line= 3
        1966175.     13938725.05        1966175.       13938625.
        1966175.     13938525.05
#Sta/Elev= 28
    4900 1761.52  4902.5 1761.52    4910 1760.43  4916.6  1759.3    4920 1758.72
    4930 1756.28    4940  1753.4    4950 1749.84    4970 1745.19    4980 1743.49
    4990 1742.06  4995.5 1740.68  4995.8 1740.18  4999.3 1740.18  4999.5 1740.68
    5000 1740.68  5002.5 1740.68    5010 1740.97    5020 1740.86    5030  1741.7
    5040 1751.26    5050 1757.44    5060 1759.45    5070  1759.8    5080 1759.95
    5090 1760.02  5097.5  1760.3    5100  1760.3
#Mann= 4 ,-1 , 0
    4900    .035       0  4916.6     .07       0  4995.5     .05       0
  4999.5     .07       0
Bank Sta=4995.5,4999.5
XS Rating Curve= 0 ,0
Exp/Cntr=0.3,0.1

Type RM Length L Ch R = 1 ,216     ,0,0,0
BEGIN DESCRIPTION:
Stream0033 0.0
END DESCRIPTION:
XS GIS Cut Line= 3
       1966425.4     13938849.97      1966472.29     13938586.91
      1966269.17     13938347.34
#Sta/Elev= 30
  4655.6  1761.3  4678.8  1761.4  4731.8 1758.21  4762.2 1751.92  4791.7 1748.08
  4796.8 1744.97  4802.9 1743.51  4833.3 1740.13  4859.5 1738.76  4882.1 1738.81
    4972 1739.26  4978.5 1737.56  4984.3 1734.83  4984.5 1734.33  4988.3 1734.83
  4992.8 1736.08  5007.1 1737.21    5050 1738.29  5056.5 1740.24  5064.2 1740.87
  5070.8 1744.68  5078.5 1745.37  5085.1 1748.89  5092.8 1749.33  5099.4 1752.31
  5107.1 1752.63  5113.7 1754.43  5121.4 1753.95  5148.8 1755.84  5236.9 1757.96
#Mann= 5 ,-1 , 0
  4655.6     .07       0  4859.5    .035       0  4882.1    .035       0
  4984.3    .035       0  4988.3    .035       0
Bank Sta=4984.3,4988.3
XS Rating Curve= 0 ,0
Exp/Cntr=0.3,0.1

Chan Stop Cuts=-1
Use User Specified Reach Order=0
Composite Channel Slope=5