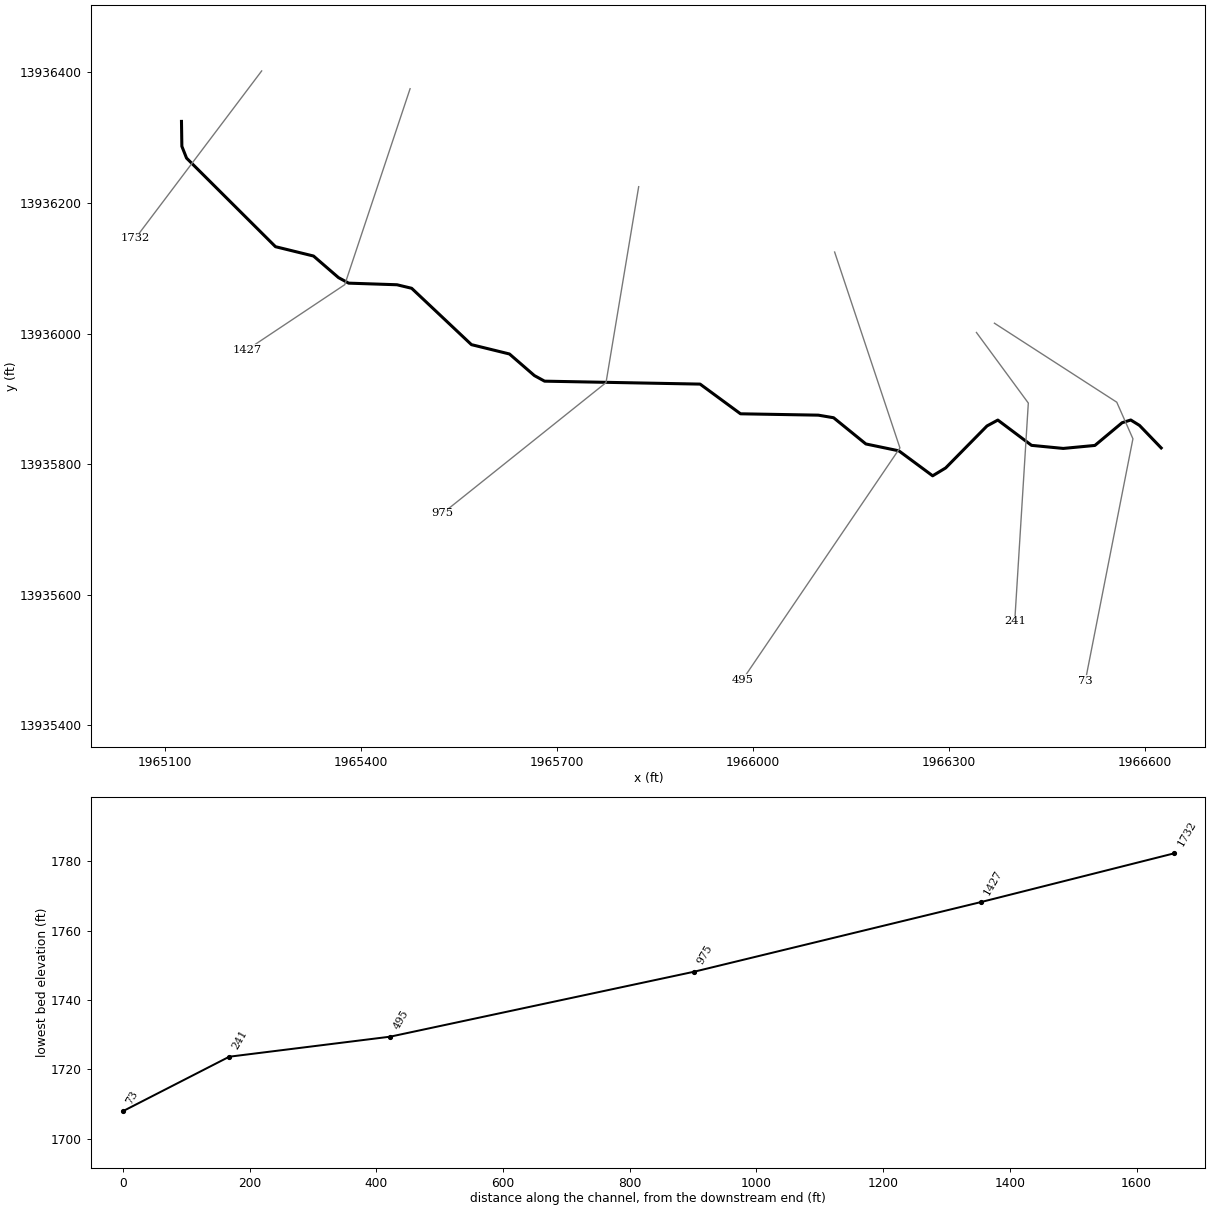
--- Stream0034.prj (project) ---

Proj Title=Stream0034 Base Level Engineering
Current Plan=p01
Default Exp/Contr=0.3,0.1
English Units
Geom File=g01
Flow File=f01
Plan File=p01
BEGIN DESCRIPTION:
Stream0034
END DESCRIPTION:

--- Stream0034.p01 (plan) ---

Plan Title=Multiple Run
Short Identifier=Multiple
Geom File=g01
Flow File=f01
Subcritical Flow
K Sum by GR= 0
Std Step Tol= 0.01
Critical Tol= 0.01
Num of Std Step Trials= 20
Max Error Tol= 0.3
Flow Tol Ratio= 0.001
Split Flow NTrial= 30
Split Flow Tol= 0.02
Split Flow Ratio= 0.02
Log Output Level= 0
Friction Slope Method= 1
Unsteady Friction Slope Method= 2
Unsteady Bridges Friction Slope Method= 1
Parabolic Critical Depth
Global Vel Dist=  1 , 1 , 1
Global Log Level= 0
CheckData=True
Encroach Param= -1, 0, 0, 0
BEGIN DESCRIPTION:
Multiple Run
END DESCRIPTION:

--- Stream0034.f01 (steady flow) ---

Flow Title=Multiple
Number of Profiles=7
Profile Names=10-year,25-year,50-year,1pct_min,100-year,1pct_plu,500-year
River Rch & RM= Stream0034,Reach-1,1732
     498     811    1098     724    1444    2882    2453
Boundary for River Rch & Prof#=Stream0034,Reach-1,1
Up Type=0
Dn Type=3
Dn Slope=0.005
Boundary for River Rch & Prof#=Stream0034,Reach-1,2
Up Type=0
Dn Type=3
Dn Slope=0.005
Boundary for River Rch & Prof#=Stream0034,Reach-1,3
Up Type=0
Dn Type=3
Dn Slope=0.005
Boundary for River Rch & Prof#=Stream0034,Reach-1,4
Up Type=0
Dn Type=3
Dn Slope=0.005
Boundary for River Rch & Prof#=Stream0034,Reach-1,5
Up Type=0
Dn Type=3
Dn Slope=0.005
Boundary for River Rch & Prof#=Stream0034,Reach-1,6
Up Type=0
Dn Type=3
Dn Slope=0.005
Boundary for River Rch & Prof#=Stream0034,Reach-1,7
Up Type=0
Dn Type=3
Dn Slope=0.005

--- Stream0034.g01 (geometry) ---

Geom Title=Existing Conditions

River Reach=Stream0034,Reach-1
Reach XY= 30
      1965125.00     13936325.00      1965125.59     13936286.84
      1965132.76     13936268.79      1965268.94     13936133.14
      1965327.17     13936118.86      1965365.35     13936085.84
      1965380.97     13936077.33      1965454.95     13936074.87
      1965477.42     13936069.46      1965568.95     13935983.16
      1965627.17     13935968.86      1965665.33     13935935.79
      1965680.93     13935927.24      1965919.06     13935922.74
      1965980.94     13935877.27      1966100.08     13935875.19
      1966123.44     13935871.24      1966172.83     13935831.09
      1966223.37     13935820.57      1966275.09     13935782.31
      1966295.03     13935794.37      1966358.29     13935858.64
      1966374.90     13935867.66      1966426.50     13935828.95
      1966475.00     13935824.24      1966523.52     13935828.82
      1966565.20     13935863.62      1966578.45     13935867.76
      1966591.84     13935859.46      1966625.00     13935825.00

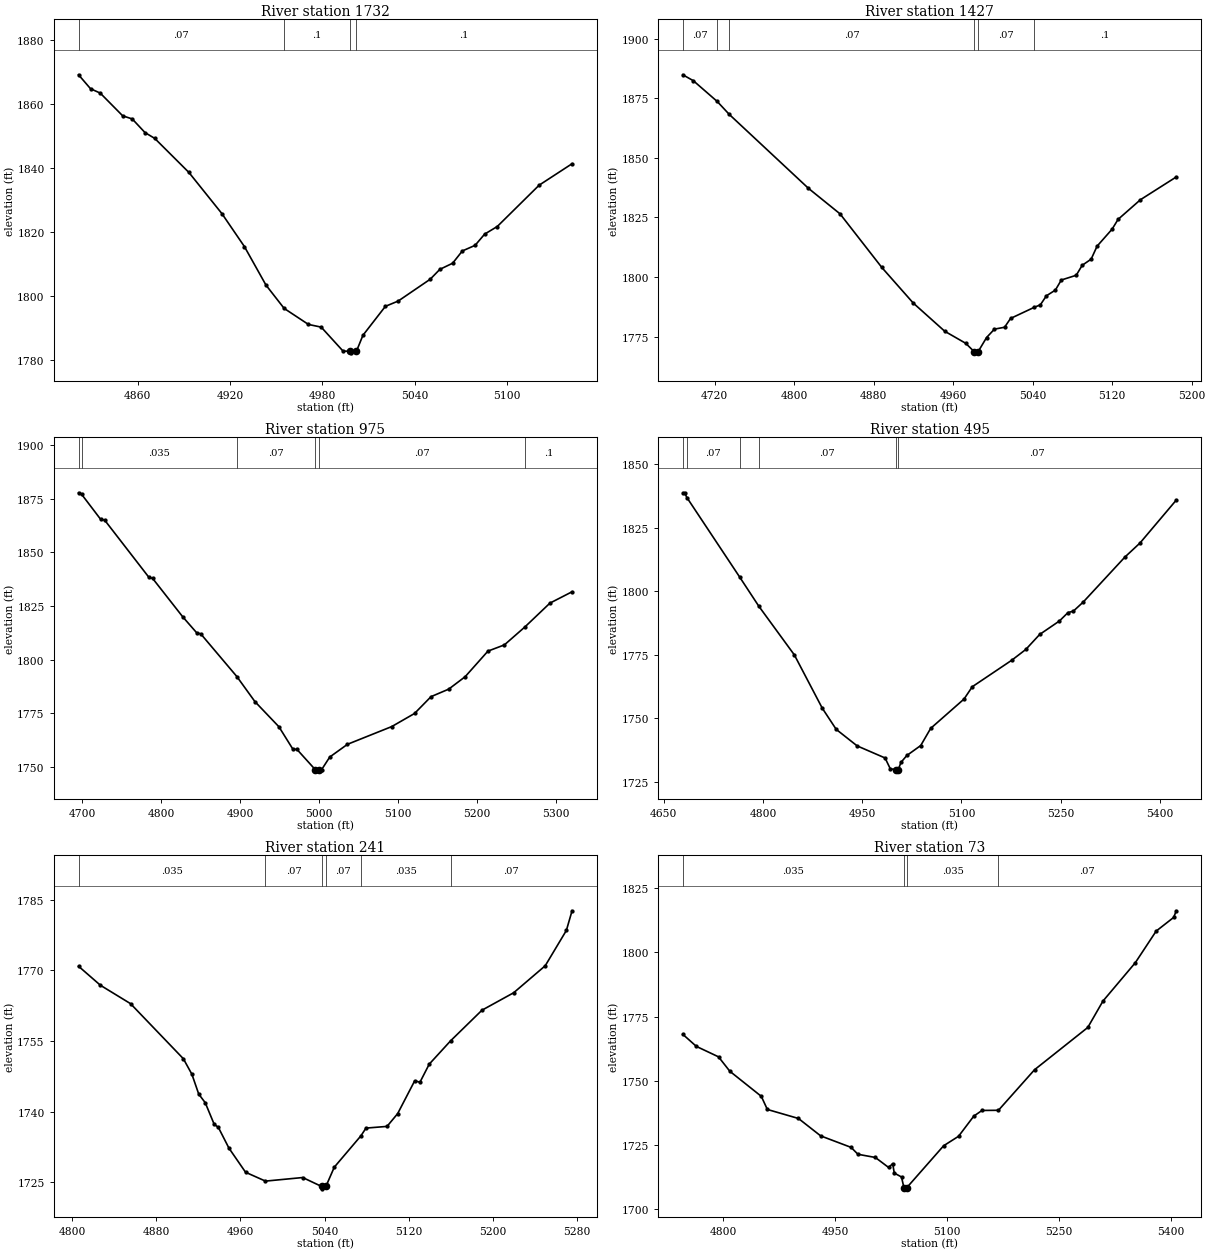
Type RM Length L Ch R = 1,1732,305,305,305
BEGIN DESCRIPTION:
Stream0034 4.0
END DESCRIPTION:
XS GIS Cut Line= 2
      1965247.75     13936402.26      1965054.64     13936146.22
#Sta/Elev= 30
  4821.5 1869.25  4829.3 1864.89  4835.6 1863.52  4850.2 1856.41  4856.4 1855.44
  4864.7 1851.17  4871.0 1849.36  4893.2 1838.72  4914.7 1825.81  4929.3 1815.52
  4943.3 1803.48  4955.1 1796.19  4970.9 1791.17  4979.2 1790.33  4993.4 1782.83
  4998.1 1782.79  4998.3 1782.29  5002.1 1782.79  5006.3 1787.77  5020.9 1796.83
  5029.2 1798.48  5050.0 1805.30  5056.3 1808.40  5064.6 1810.32  5070.9 1814.15
  5079.2 1815.91  5085.4 1819.42  5093.6 1821.80  5120.8 1834.72  5142.2 1841.43
#Mann=4,-1,0
  4821.5    0.07       0  4955.1     0.1       0  4998.1    0.05       0
  5002.1     0.1       0
Bank Sta=4998.1,5002.1
Exp/Cntr=0.3,0.1

Type RM Length L Ch R = 1,1427,452,452,452
BEGIN DESCRIPTION:
Stream0034 3.0
END DESCRIPTION:
XS GIS Cut Line= 3
      1965475.01     13936375.04      1965375.00     13936075.00
      1965224.96     13935974.97
#Sta/Elev= 30
  4687.9 1884.84  4698.5 1882.36  4722.5 1873.67  4734.7 1868.21  4814.4 1837.20
  4846.1 1826.53  4888.2 1804.02  4919.8 1789.11  4951.5 1777.28  4972.6 1772.23
  4981.1 1768.73  4981.3 1768.23  4985.1 1768.73  4993.6 1774.66  5001.5 1778.17
  5011.7 1778.96  5017.7 1782.65  5041.6 1787.33  5047.7 1788.36  5053.8 1792.15
  5062.8 1794.54  5068.8 1798.77  5083.8 1800.76  5089.8 1804.94  5098.8 1807.52
  5104.8 1812.97  5119.9 1820.10  5125.9 1824.20  5148.4 1832.44  5184.5 1842.00
#Mann=6,-1,0
  4687.9    0.07       0  4722.5     0.1       0  4734.7    0.07       0
  4981.1    0.05       0  4985.1    0.07       0  5041.6     0.1       0
Bank Sta=4981.1,4985.1
Exp/Cntr=0.3,0.1

Type RM Length L Ch R = 1,975,480,480,480
BEGIN DESCRIPTION:
Stream0034 2.0
END DESCRIPTION:
XS GIS Cut Line= 3
      1965825.01     13936225.05      1965775.00     13935925.00
      1965525.03     13935725.02
#Sta/Elev= 30
  4695.7 1877.79  4699.6 1877.08  4723.6 1865.45  4728.7 1865.07  4784.5 1838.48
  4789.5 1837.84  4827.5 1819.97  4845.3 1812.47  4850.3 1812.03  4896.0 1792.11
  4918.8 1780.46  4949.2 1768.71  4966.9 1758.24  4972.0 1758.17  4995.3 1748.67
  4995.6 1748.17  4999.3 1748.67  5003.1 1748.67  5013.5 1754.61  5035.9 1760.54
  5091.9 1768.80  5120.7 1774.90  5141.6 1782.75  5164.0 1786.26  5184.8 1792.06
  5213.6 1803.98  5234.4 1806.88  5260.4 1815.26  5292.0 1826.35  5320.0 1831.64
#Mann=6,-1,0
  4695.7    0.07       0  4699.6   0.035       0  4896.0    0.07       0
  4995.3    0.05       0  4999.3    0.07       0  5260.4     0.1       0
Bank Sta=4995.3,4999.3
Exp/Cntr=0.3,0.1

Type RM Length L Ch R = 1,495,254,254,254
BEGIN DESCRIPTION:
Stream0034 1.0
END DESCRIPTION:
XS GIS Cut Line= 3
      1966125.01     13936124.98      1966225.00     13935825.00
      1965983.74     13935469.55
#Sta/Elev= 30
  4678.9 1838.65  4681.5 1838.65  4685.2 1836.74  4764.7 1805.61  4793.8 1794.09
  4847.5 1774.96  4889.7 1754.03  4910.8 1745.70  4942.4 1739.22  4984.6 1734.47
  4992.5 1730.21  5000.6 1729.92  5000.8 1729.42  5004.6 1729.92  5008.6 1732.74
  5017.5 1735.45  5038.5 1739.37  5053.5 1746.10  5103.9 1757.62  5116.4 1762.46
  5176.2 1772.90  5197.2 1777.09  5218.2 1782.99  5248.1 1788.29  5261.0 1791.59
  5269.1 1792.15  5284.0 1795.71  5347.0 1813.39  5369.8 1818.91  5424.7 1835.79
#Mann=6,-1,0
  4678.9   0.035       0  4685.2    0.07       0  4764.7   0.035       0
  4793.8    0.07       0  5000.6    0.05       0  5004.6    0.07       0
Bank Sta=5000.6,5004.6
Exp/Cntr=0.3,0.1

Type RM Length L Ch R = 1,241,168,168,168
BEGIN DESCRIPTION:
Stream0034 T
END DESCRIPTION:
XS GIS Cut Line= 3
      1966342.15     13936001.79      1966421.58     13935893.71
      1966400.78     13935559.58
#Sta/Elev= 30
  4806.2 1770.88  4827.0 1766.84  4855.6 1762.94  4905.8 1751.25  4913.9 1747.96
  4920.4 1743.75  4926.6 1741.91  4935.1 1737.33  4939.0 1736.70  4949.1 1732.28
  4964.9 1727.16  4983.8 1725.28  5019.2 1726.04  5037.2 1724.14  5037.5 1723.64
  5041.2 1724.14  5049.2 1728.24  5074.5 1734.89  5079.3 1736.53  5099.3 1736.89
  5109.4 1739.60  5125.6 1746.57  5130.6 1746.27  5139.4 1750.10  5159.7 1755.05
  5189.5 1761.55  5219.6 1765.25  5249.6 1770.98  5269.7 1778.48  5275.1 1782.65
#Mann=6,-1,0
  4806.2   0.035       0  4983.8    0.07       0  5037.2    0.05       0
  5041.2    0.07       0  5074.5   0.035       0  5159.7    0.07       0
Bank Sta=5037.2,5041.2
Exp/Cntr=0.3,0.1

Type RM Length L Ch R = 1,73,0,0,0
BEGIN DESCRIPTION:
Stream0034 0.0
END DESCRIPTION:
XS GIS Cut Line= 4
      1966369.71     13936015.97      1966557.00     13935895.01
      1966581.74     13935839.02      1966508.91     13935468.48
#Sta/Elev= 30
  4745.7 1768.11  4763.9 1763.40  4793.6 1759.33  4808.8 1753.71  4851.0 1743.94
  4859.1 1738.83  4900.8 1735.32  4930.6 1728.54  4971.4 1724.06  4980.6 1721.37
  5003.9 1720.13  5021.7 1716.24  5027.2 1717.72  5029.3 1714.05  5039.0 1712.53
  5042.2 1708.41  5042.4 1707.91  5046.2 1708.41  5095.5 1724.69  5115.5 1728.38
  5135.9 1736.22  5146.9 1738.44  5169.0 1738.51  5217.4 1754.30  5288.8 1770.77
  5309.1 1781.03  5352.5 1795.98  5380.5 1808.31  5403.9 1813.62  5407.5 1816.22
#Mann=4,-1,0
  4745.7   0.035       0  5042.2   0.035       0  5046.2   0.035       0
  5169.0    0.07       0
Bank Sta=5042.2,5046.2
Exp/Cntr=0.3,0.1

Chan Stop Cuts=-1