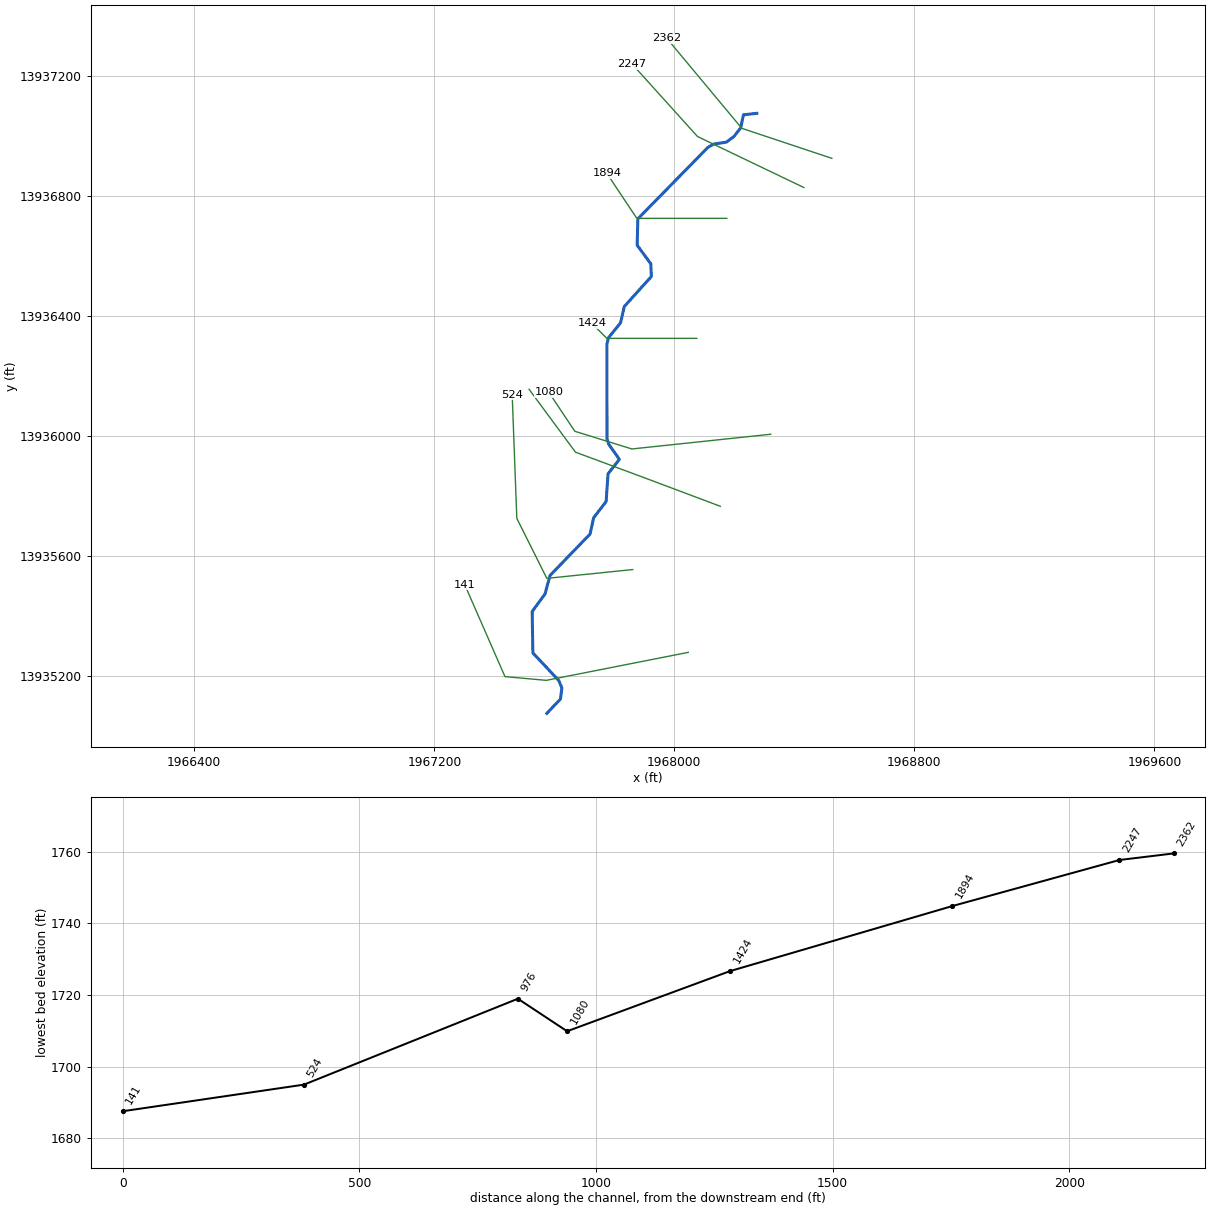
--- Stream0035.prj (project) ---

Proj Title=Stream0035 Base Level Engineering
Current Plan=p01
Default Exp/Contr=0.3,0.1
English Units
Geom File=g01
Flow File=f01
Plan File=p01
BEGIN DESCRIPTION:
Stream0035
END DESCRIPTION:

--- Stream0035.p01 (plan) ---

Plan Title=Multiple Run
Short Identifier=Multiple
Geom File=g01
Flow File=f01
Subcritical Flow
K Sum by GR= 0
Std Step Tol= 0.01
Critical Tol= 0.01
Num of Std Step Trials= 20
Max Error Tol= 0.3
Flow Tol Ratio= 0.001
Split Flow NTrial= 30
Split Flow Tol= 0.02
Split Flow Ratio= 0.02
Log Output Level= 0
Friction Slope Method= 1
Unsteady Friction Slope Method= 2
Unsteady Bridges Friction Slope Method= 1
Parabolic Critical Depth
Global Vel Dist=  1 , 1 , 1
Global Log Level= 0
CheckData=True
Encroach Param= -1, 0, 0, 0
BEGIN DESCRIPTION:
Multiple Run
END DESCRIPTION:

--- Stream0035.f01 (steady flow) ---

Flow Title=Multiple
Number of Profiles=7
Profile Names=10-year,25-year,50-year,1pct_min,100-year,1pct_plu,500-year
River Rch & RM= Stream0035,Reach-1,2362
     479     772    1038     679    1354    2702    2265
Boundary for River Rch & Prof#=Stream0035,Reach-1,1
Up Type=0
Dn Type=3
Dn Slope=0.005
Boundary for River Rch & Prof#=Stream0035,Reach-1,2
Up Type=0
Dn Type=3
Dn Slope=0.005
Boundary for River Rch & Prof#=Stream0035,Reach-1,3
Up Type=0
Dn Type=3
Dn Slope=0.005
Boundary for River Rch & Prof#=Stream0035,Reach-1,4
Up Type=0
Dn Type=3
Dn Slope=0.005
Boundary for River Rch & Prof#=Stream0035,Reach-1,5
Up Type=0
Dn Type=3
Dn Slope=0.005
Boundary for River Rch & Prof#=Stream0035,Reach-1,6
Up Type=0
Dn Type=3
Dn Slope=0.005
Boundary for River Rch & Prof#=Stream0035,Reach-1,7
Up Type=0
Dn Type=3
Dn Slope=0.005

--- Stream0035.g01 (geometry) ---

Geom Title=Existing Conditions

River Reach=Stream0035,Reach-1
Reach XY= 30
      1968275.00     13937075.00      1968230.34     13937070.04
      1968221.32     13937026.56      1968198.83     13936997.90
      1968173.56     13936978.90      1968131.08     13936972.46
      1968111.80     13936961.37      1967878.46     13936723.50
      1967876.12     13936635.55      1967921.66     13936573.25
      1967923.37     13936531.04      1967833.16     13936431.05
      1967820.78     13936376.75      1967780.71     13936327.35
      1967775.06     13936304.97      1967775.66     13935990.16
      1967781.02     13935972.55      1967816.92     13935921.70
      1967779.09     13935873.50      1967772.67     13935780.97
      1967731.14     13935727.17      1967719.17     13935672.70
      1967585.76     13935534.68      1967568.86     13935472.83
      1967526.19     13935414.50      1967528.54     13935276.47
      1967614.78     13935184.70      1967625.18     13935159.74
      1967620.43     13935122.65      1967575.00     13935075.00

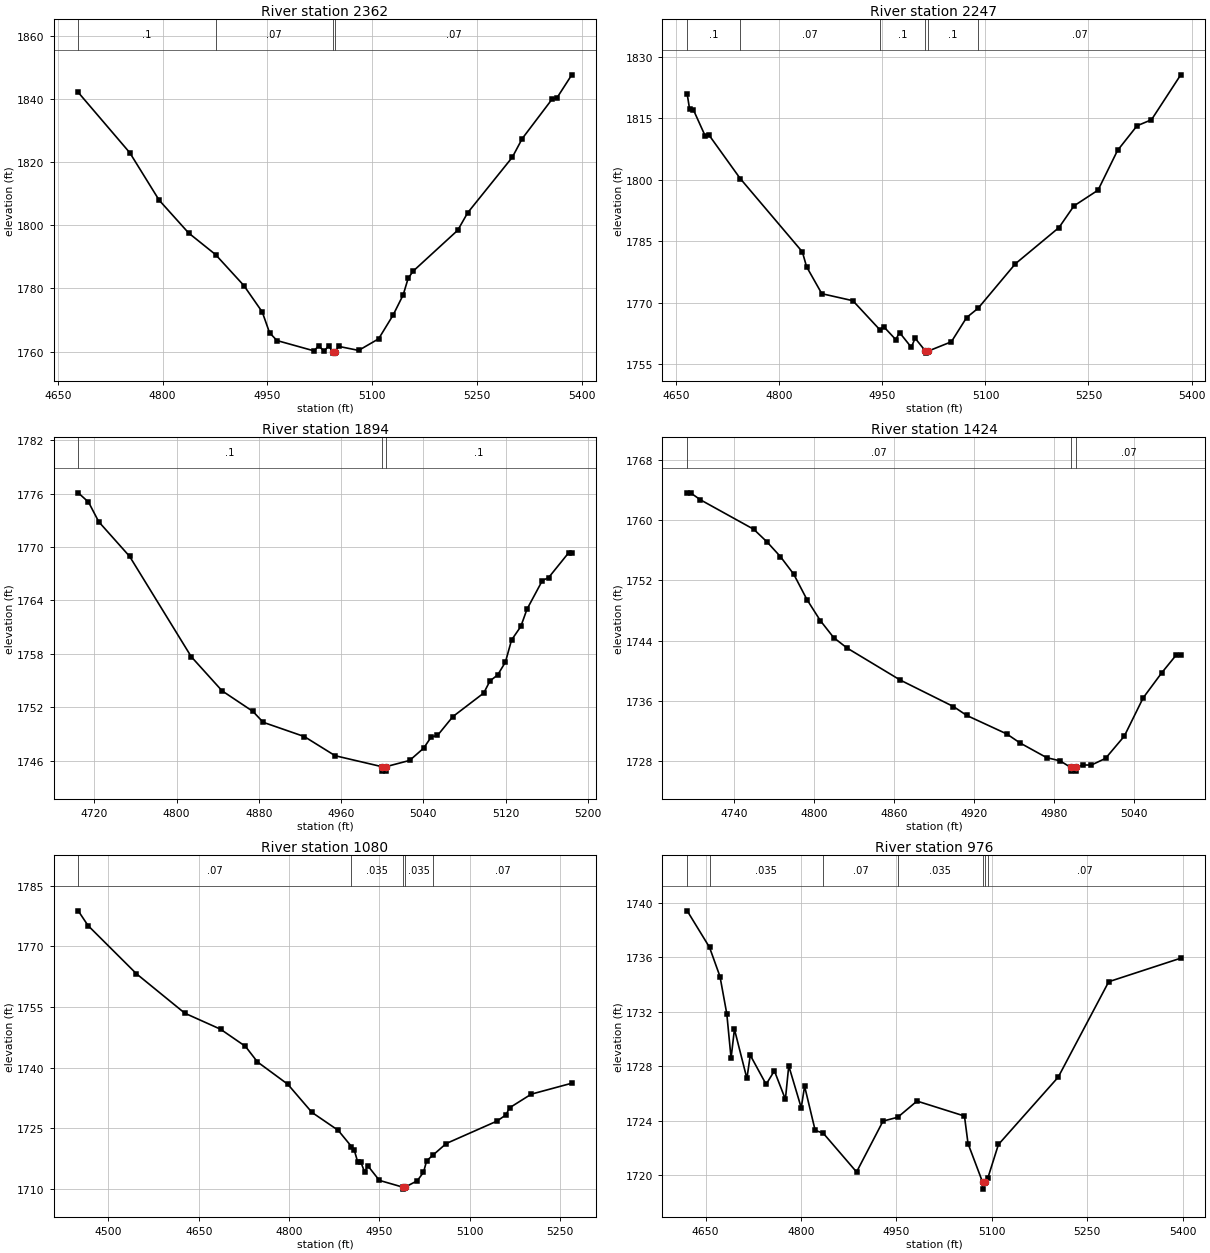
Type RM Length L Ch R = 1,2362,115,115,115
BEGIN DESCRIPTION:
Stream0035 5.0
END DESCRIPTION:
XS GIS Cut Line= 3
      1968524.98     13936925.01      1968225.00     13937025.00
      1967975.01     13937324.98
#Sta/Elev= 30
  4679.1 1842.06  4752.9 1822.97  4795.0 1807.94  4837.2 1797.56  4875.7 1790.74
  4916.3 1780.93  4942.6 1772.57  4953.1 1765.98  4963.7 1763.53  5016.8 1760.26
  5023.3 1761.88  5031.1 1760.17  5037.6 1761.83  5043.4 1760.05  5043.7 1759.55
  5047.4 1760.05  5051.9 1761.69  5080.6 1760.41  5109.2 1764.07  5130.0 1771.60
  5144.4 1777.99  5151.5 1783.21  5158.7 1785.50  5222.5 1798.43  5236.8 1803.98
  5300.6 1821.51  5314.9 1827.45  5357.8 1839.97  5364.3 1840.23  5385.8 1847.61
#Mann=4,-1,0
  4679.1     0.1       0  4875.7    0.07       0  5043.4    0.05       0
  5047.4    0.07       0
Bank Sta=5043.4,5047.4
Exp/Cntr=0.3,0.1

Type RM Length L Ch R = 1,2247,353,353,353
BEGIN DESCRIPTION:
Mapping XS c489ef7e
END DESCRIPTION:
XS GIS Cut Line= 3
      1968431.76     13936827.76      1968077.23     13936997.73
      1967859.30     13937239.28
#Sta/Elev= 30
  4665.8 1820.99  4669.4 1817.21  4674.9 1817.10  4692.0 1810.75  4697.6 1810.95
  4743.0 1800.34  4833.5 1782.43  4839.6 1778.81  4861.8 1772.22  4907.0 1770.51
  4946.2 1763.43  4952.3 1764.10  4969.4 1761.03  4975.0 1762.73  4992.1 1759.13
  4997.6 1761.36  5012.7 1758.21  5013.0 1757.71  5016.7 1758.21  5050.4 1760.48
  5072.6 1766.40  5089.4 1768.68  5143.6 1779.53  5207.1 1788.38  5228.8 1793.65
  5263.9 1797.50  5292.3 1807.20  5320.7 1813.22  5341.7 1814.69  5384.3 1825.66
#Mann=6,-1,0
  4665.8     0.1       0  4743.0    0.07       0  4946.2     0.1       0
  5012.7    0.05       0  5016.7     0.1       0  5089.4    0.07       0
Bank Sta=5012.7,5016.7
Exp/Cntr=0.3,0.1

Type RM Length L Ch R = 1,1894,470,470,470
BEGIN DESCRIPTION:
Stream0035 4.0
END DESCRIPTION:
XS GIS Cut Line= 3
      1968175.00     13936725.00      1967875.00     13936725.00
      1967774.99     13936875.02
#Sta/Elev= 30
  4704.2 1776.08  4714.2 1775.04  4724.2 1772.83  4754.2 1768.95  4814.2 1757.69
  4844.2 1753.86  4874.2 1751.55  4884.2 1750.33  4924.2 1748.73  4954.2 1746.58
  4999.7 1745.35  4999.9 1744.85  5003.4 1744.85  5003.7 1745.35  5026.7 1746.05
  5040.3 1747.42  5047.8 1748.70  5053.8 1748.85  5068.8 1750.97  5098.8 1753.61
  5104.9 1754.97  5112.4 1755.65  5119.9 1757.08  5125.9 1759.57  5134.9 1761.08
  5140.9 1763.02  5155.9 1766.24  5161.9 1766.56  5181.5 1769.36  5184.5 1769.36
#Mann=3,-1,0
  4704.2     0.1       0  4999.7    0.05       0  5003.7     0.1       0
Bank Sta=4999.7,5003.7
Exp/Cntr=0.3,0.1

Type RM Length L Ch R = 1,1424,344,344,344
BEGIN DESCRIPTION:
Stream0035 3.0
END DESCRIPTION:
XS GIS Cut Line= 3
      1968075.03     13936325.00      1967775.00     13936325.00
      1967725.03     13936374.97
#Sta/Elev= 30
  4704.5 1763.61  4707.0 1763.61  4714.5 1762.68  4754.5 1758.77  4764.5 1757.09
  4774.5 1755.15  4784.5 1752.82  4794.5 1749.43  4804.5 1746.65  4814.5 1744.40
  4824.5 1743.02  4864.5 1738.76  4904.5 1735.24  4914.5 1734.06  4944.5 1731.61
  4954.5 1730.41  4974.5 1728.46  4984.5 1728.04  4992.5 1727.17  4992.8 1726.67
  4996.3 1726.67  4996.5 1727.17  5002.0 1727.48  5008.1 1727.48  5018.7 1728.36
  5032.8 1731.31  5047.0 1736.40  5061.1 1739.76  5071.7 1742.06  5075.2 1742.06
#Mann=3,-1,0
  4704.5    0.07       0  4992.5    0.05       0  4996.5    0.07       0
Bank Sta=4992.5,4996.5
Exp/Cntr=0.3,0.1

Type RM Length L Ch R = 1,1080,104,104,104
BEGIN DESCRIPTION:
Stream0035 2.1
END DESCRIPTION:
XS GIS Cut Line= 4
      1968321.21     13936005.34      1967858.51     13935956.32
      1967668.36     13936015.24      1967581.90     13936144.89
#Sta/Elev= 30
  4449.7 1778.83  4466.0 1775.18  4546.5 1763.23  4626.9 1753.46  4686.2 1749.50
  4727.5 1745.26  4747.6 1741.39  4797.9 1735.87  4838.1 1728.89  4881.7 1724.45
  4903.8 1720.43  4908.5 1719.51  4914.2 1716.58  4919.4 1716.58  4925.7 1714.06
  4930.9 1715.68  4950.1 1712.05  4988.9 1710.38  4989.1 1709.88  4992.9 1710.38
  5012.9 1711.93  5023.4 1714.02  5028.7 1716.89  5039.6 1718.36  5061.3 1721.18
  5145.5 1726.73  5160.5 1728.27  5166.5 1730.03  5202.6 1733.41  5269.9 1736.12
#Mann=5,-1,0
  4449.7    0.07       0  4903.8   0.035       0  4988.9   0.035       0
  4992.9   0.035       0  5039.6    0.07       0
Bank Sta=4988.9,4992.9
Exp/Cntr=0.3,0.1

Type RM Length L Ch R = 1,976,452,452,452
BEGIN DESCRIPTION:
Stream0035 2.0
END DESCRIPTION:
XS GIS Cut Line= 4
      1968153.31     13935765.26      1967907.05     13935857.78
      1967670.50     13935945.67      1967515.83     13936155.26
#Sta/Elev= 30
  4621.1 1739.41  4656.2 1736.73  4672.7 1734.58  4683.4 1731.84  4690.1 1728.58
  4695.4 1730.71  4715.0 1727.09  4720.3 1728.80  4745.2 1726.66  4758.2 1727.65
  4775.5 1725.56  4780.8 1728.02  4800.4 1724.94  4805.7 1726.52  4822.3 1723.28
  4835.0 1723.07  4887.4 1720.22  4929.0 1723.96  4952.1 1724.24  4982.4 1725.43
  5057.0 1724.33  5062.6 1722.31  5085.6 1719.46  5085.9 1718.96  5089.6 1719.46
  5094.0 1719.81  5110.4 1722.24  5204.4 1727.19  5283.8 1734.20  5397.0 1735.93
#Mann=7,-1,0
  4621.1    0.07       0  4656.2   0.035       0  4835.0    0.07       0
  4952.1   0.035       0  5085.6   0.035       0  5089.6   0.035       0
  5094.0    0.07       0
Bank Sta=5085.6,5089.6
Exp/Cntr=0.3,0.1

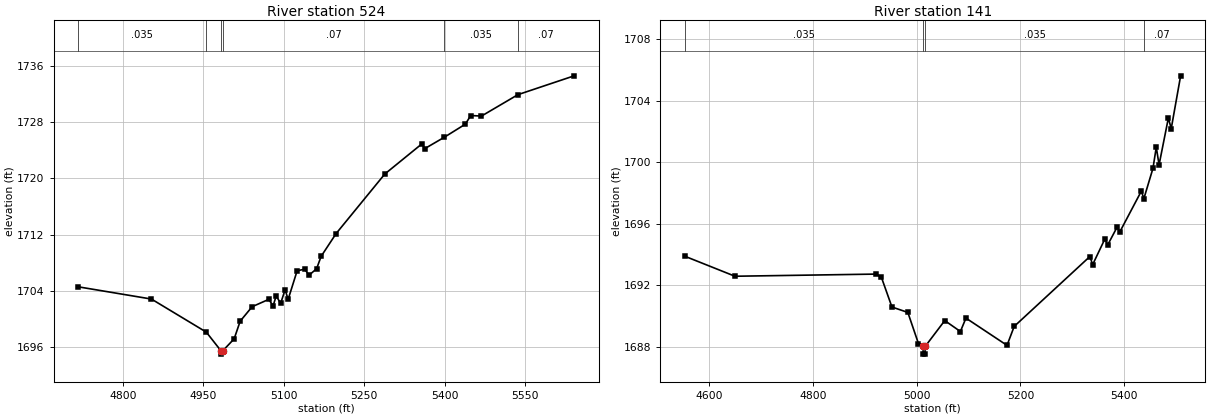
Type RM Length L Ch R = 1,524,383,383,383
BEGIN DESCRIPTION:
Stream0035 1.0
END DESCRIPTION:
XS GIS Cut Line= 4
      1967861.20     13935554.37      1967575.00     13935525.00
      1967475.00     13935725.00      1967459.56     13936137.71
#Sta/Elev= 30
  4717.3 1704.55  4853.6 1702.81  4955.9 1698.10  4982.9 1695.47  4983.1 1694.97
  4986.9 1695.47  5007.8 1697.15  5019.0 1699.66  5041.3 1701.72  5072.1 1702.76
  5080.5 1701.86  5086.1 1703.26  5094.4 1702.20  5102.8 1704.13  5108.4 1702.76
  5125.2 1706.84  5139.2 1707.06  5147.5 1706.21  5161.5 1707.13  5169.9 1708.89
  5197.9 1712.14  5288.6 1720.61  5358.0 1724.92  5363.0 1724.22  5399.2 1725.83
  5438.8 1727.71  5448.8 1728.94  5468.8 1728.86  5536.8 1731.91  5641.6 1734.59
#Mann=6,-1,0
  4717.3   0.035       0  4955.9    0.07       0  4982.9    0.05       0
  4986.9    0.07       0  5399.2   0.035       0  5536.8    0.07       0
Bank Sta=4982.9,4986.9
Exp/Cntr=0.3,0.1

Type RM Length L Ch R = 1,141,0,0,0
BEGIN DESCRIPTION:
Sstream0035 0.0
END DESCRIPTION:
XS GIS Cut Line= 4
      1968046.39     13935278.38      1967573.48     13935185.10
      1967435.57     13935197.45      1967301.48     13935503.70
#Sta/Elev= 30
  4553.6 1693.90  4650.2 1692.60  4922.0 1692.74  4932.1 1692.54  4952.5 1690.60
  4983.1 1690.25  5003.5 1688.23  5012.5 1688.04  5012.8 1687.54  5016.3 1687.54
  5016.5 1688.04  5054.2 1689.72  5084.3 1689.01  5095.0 1689.88  5174.1 1688.11
  5187.9 1689.34  5333.6 1693.88  5339.1 1693.36  5362.5 1695.02  5367.9 1694.63
  5385.9 1695.78  5391.3 1695.48  5432.6 1698.12  5437.7 1697.65  5455.2 1699.62
  5461.5 1700.98  5466.9 1699.84  5484.8 1702.88  5490.3 1702.19  5508.4 1705.62
#Mann=4,-1,0
  4553.6   0.035       0  5012.5   0.035       0  5016.5   0.035       0
  5437.7    0.07       0
Bank Sta=5012.5,5016.5
Exp/Cntr=0.3,0.1

Chan Stop Cuts=-1