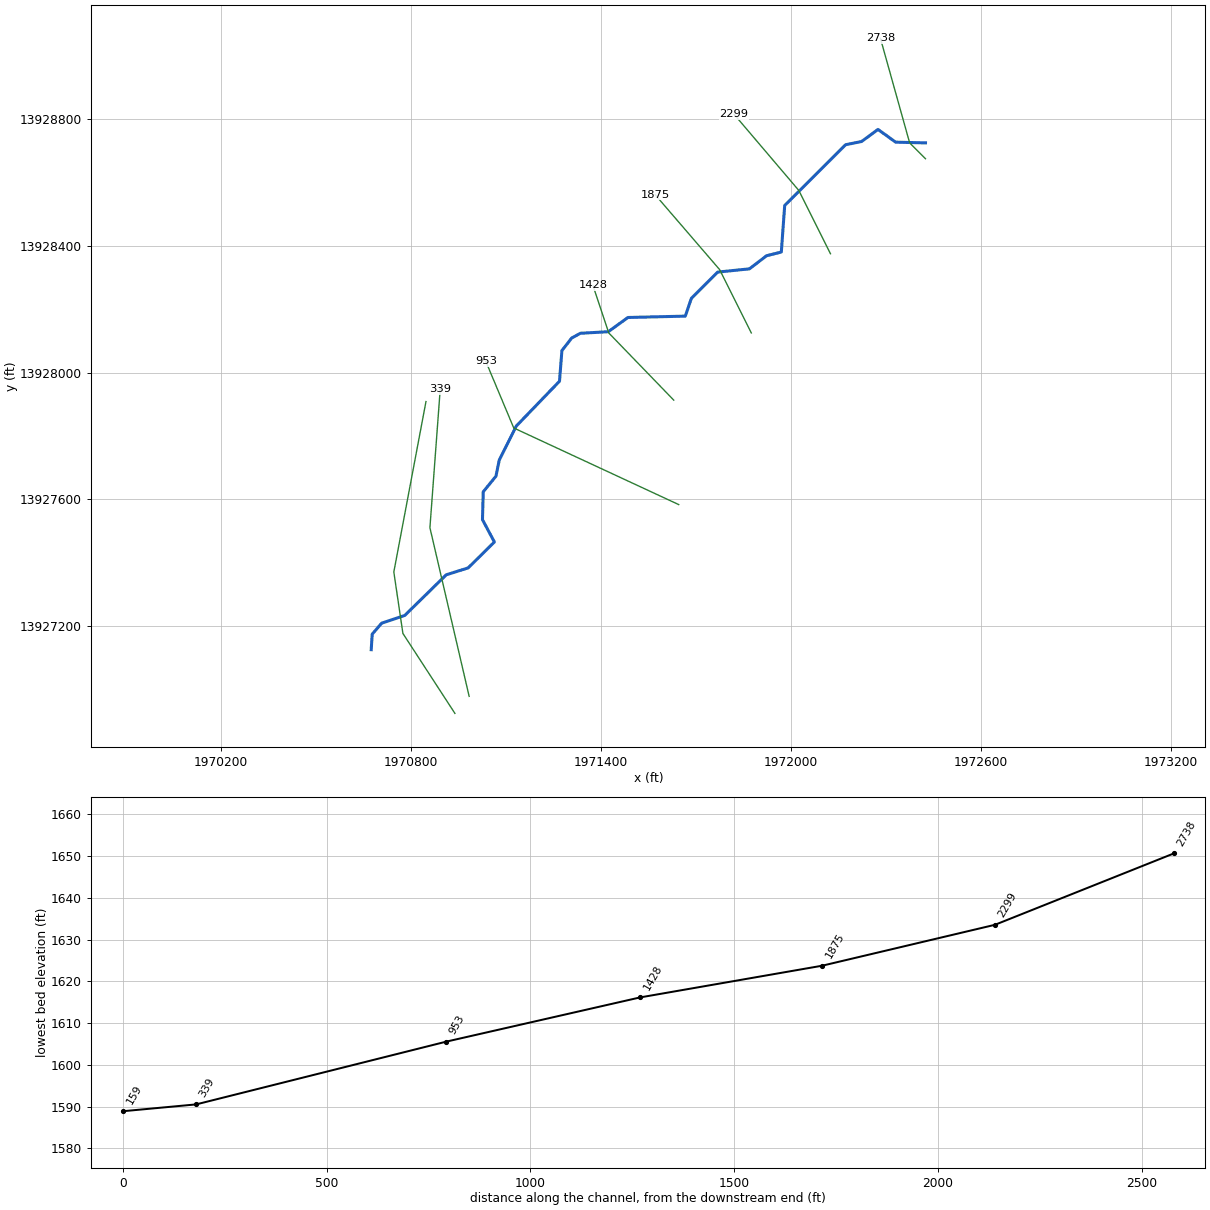
--- Stream0036.prj (project) ---

Proj Title=Stream0036 Base Level Engineering
Current Plan=p01
Default Exp/Contr=0.3,0.1
English Units
Geom File=g01
Flow File=f01
Plan File=p01
BEGIN DESCRIPTION:
Stream0036
END DESCRIPTION:

--- Stream0036.p01 (plan) ---

Plan Title=Multiple Run
Short Identifier=Multiple
Geom File=g01
Flow File=f01
Subcritical Flow
K Sum by GR= 0
Std Step Tol= 0.01
Critical Tol= 0.01
Num of Std Step Trials= 20
Max Error Tol= 0.3
Flow Tol Ratio= 0.001
Split Flow NTrial= 30
Split Flow Tol= 0.02
Split Flow Ratio= 0.02
Log Output Level= 0
Friction Slope Method= 1
Unsteady Friction Slope Method= 2
Unsteady Bridges Friction Slope Method= 1
Parabolic Critical Depth
Global Vel Dist=  1 , 1 , 1
Global Log Level= 0
CheckData=True
Encroach Param= -1, 0, 0, 0
BEGIN DESCRIPTION:
Multiple Run
END DESCRIPTION:

--- Stream0036.f01 (steady flow) ---

Flow Title=Multiple
Number of Profiles=7
Profile Names=10-year,25-year,50-year,1pct_min,100-year,1pct_plu,500-year
River Rch & RM= Stream0036,Reach-1,2738
     574     955    1313     879    1753    3499    3095
Boundary for River Rch & Prof#=Stream0036,Reach-1,1
Up Type=0
Dn Type=3
Dn Slope=0.005
Boundary for River Rch & Prof#=Stream0036,Reach-1,2
Up Type=0
Dn Type=3
Dn Slope=0.005
Boundary for River Rch & Prof#=Stream0036,Reach-1,3
Up Type=0
Dn Type=3
Dn Slope=0.005
Boundary for River Rch & Prof#=Stream0036,Reach-1,4
Up Type=0
Dn Type=3
Dn Slope=0.005
Boundary for River Rch & Prof#=Stream0036,Reach-1,5
Up Type=0
Dn Type=3
Dn Slope=0.005
Boundary for River Rch & Prof#=Stream0036,Reach-1,6
Up Type=0
Dn Type=3
Dn Slope=0.005
Boundary for River Rch & Prof#=Stream0036,Reach-1,7
Up Type=0
Dn Type=3
Dn Slope=0.005

--- Stream0036.g01 (geometry) ---

Geom Title=Existing Conditions

River Reach=Stream0036,Reach-1
Reach XY= 30
      1972425.00     13928725.00      1972330.77     13928727.34
      1972274.99     13928767.52      1972223.35     13928729.45
      1972172.71     13928719.19      1971980.47     13928527.44
      1971969.82     13928380.41      1971923.22     13928368.70
      1971869.06     13928327.32      1971768.81     13928317.14
      1971685.90     13928234.40      1971666.70     13928178.07
      1971485.51     13928173.78      1971423.40     13928128.86
      1971335.31     13928123.91      1971307.79     13928108.73
      1971277.07     13928069.31      1971269.47     13927972.58
      1971133.14     13927831.06      1971079.16     13927723.28
      1971068.88     13927672.82      1971028.68     13927623.41
      1971026.28     13927535.48      1971063.91     13927464.92
      1970981.09     13927383.16      1970911.79     13927361.37
      1970781.04     13927233.15      1970707.97     13927208.61
      1970678.14     13927173.97      1970675.00     13927125.00

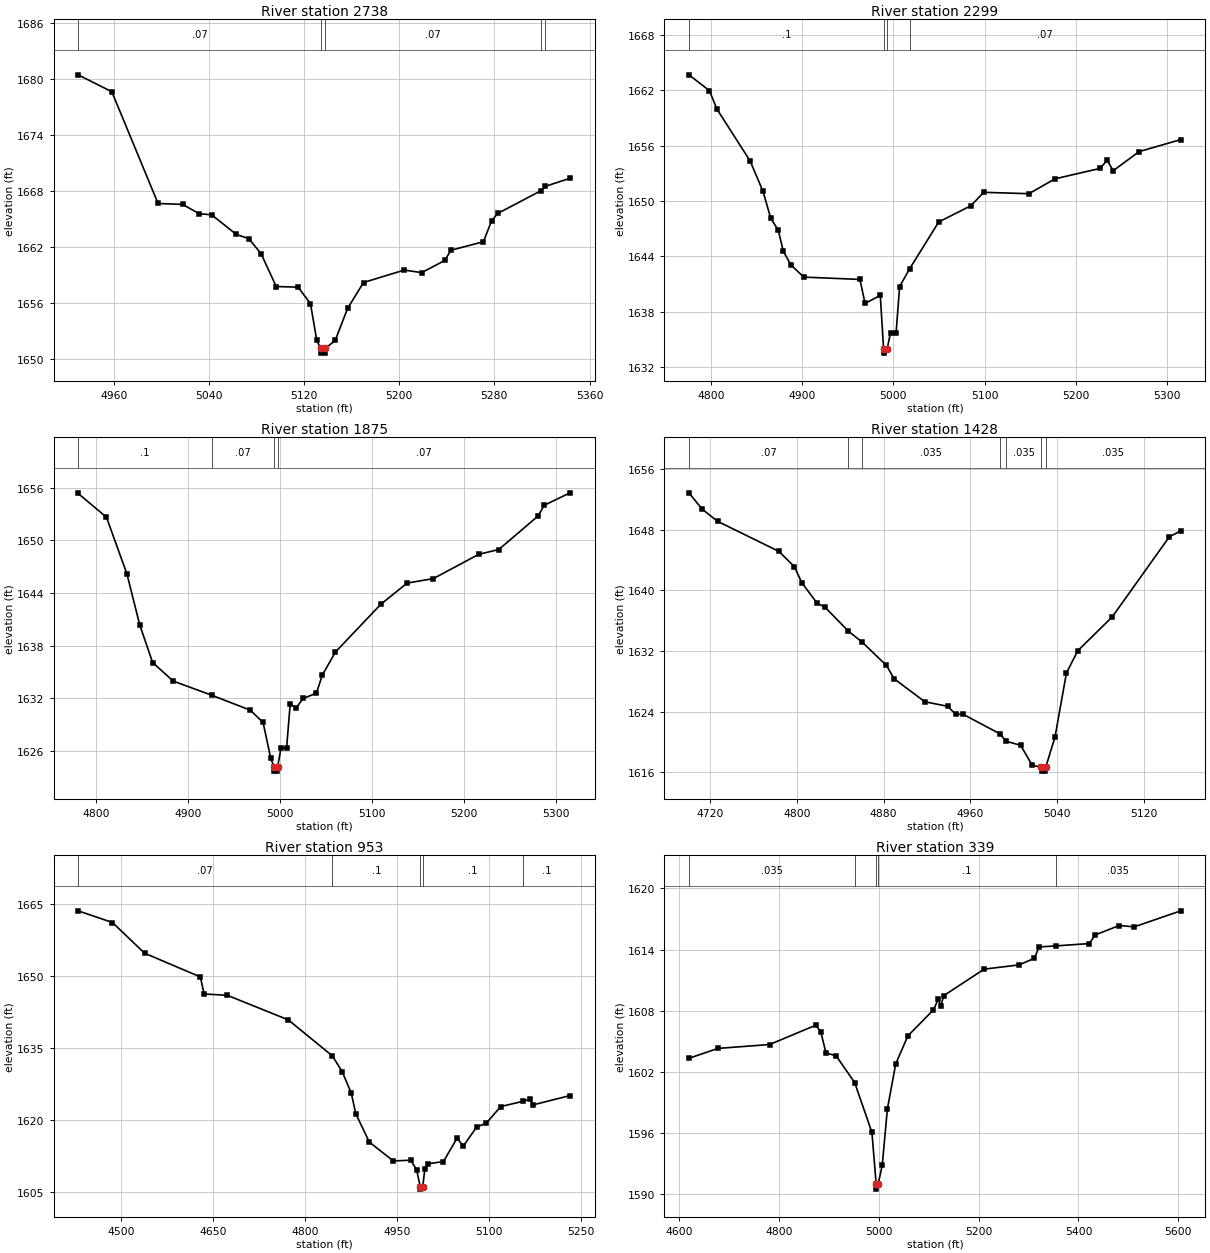
Type RM Length L Ch R = 1,2738,439,439,439
BEGIN DESCRIPTION:
Stream0036 5.0
END DESCRIPTION:
XS GIS Cut Line= 3
      1972425.00     13928675.00      1972375.00     13928725.00
      1972282.70     13929055.14
#Sta/Elev= 30
  4930.1 1680.46  4958.4 1678.65  4997.3 1666.67  5017.9 1666.57  5032.0 1665.57
  5042.3 1665.46  5063.1 1663.35  5073.5 1662.91  5083.9 1661.29  5096.6 1657.77
  5115.0 1657.70  5125.4 1655.94  5130.7 1652.00  5133.9 1651.13  5134.1 1650.63
  5137.6 1650.63  5137.9 1651.13  5146.2 1651.99  5156.6 1655.42  5170.0 1658.20
  5204.2 1659.53  5218.9 1659.26  5238.3 1660.56  5243.5 1661.66  5270.8 1662.57
  5277.7 1664.82  5282.9 1665.61  5319.4 1668.05  5322.9 1668.51  5343.6 1669.37
#Mann=5,-1,0
  4930.1    0.07       0  5133.9    0.05       0  5137.9    0.07       0
  5319.4   0.035       0  5322.9    0.07       0
Bank Sta=5133.9,5137.9
Exp/Cntr=0.3,0.1

Type RM Length L Ch R = 1,2299,424,424,424
BEGIN DESCRIPTION:
Stream0036 4.0
END DESCRIPTION:
XS GIS Cut Line= 3
      1972125.01     13928374.99      1972025.00     13928575.00
      1971820.80     13928815.09
#Sta/Elev= 30
  4776.1 1663.66  4798.5 1661.95  4806.9 1659.93  4843.2 1654.32  4857.2 1651.05
  4865.6 1648.16  4873.9 1646.84  4879.5 1644.55  4887.9 1643.07  4901.9 1641.76
  4963.4 1641.51  4969.0 1638.91  4985.7 1639.78  4989.3 1634.03  4989.6 1633.53
  4993.3 1634.03  4996.9 1635.74  5003.0 1635.74  5006.9 1640.74  5017.9 1642.67
  5049.7 1647.73  5084.8 1649.48  5099.1 1650.94  5148.5 1650.79  5177.1 1652.40
  5226.5 1653.53  5234.2 1654.42  5240.8 1653.28  5269.3 1655.35  5314.9 1656.65
#Mann=4,-1,0
  4776.1     0.1       0  4989.3    0.05       0  4993.3     0.1       0
  5017.9    0.07       0
Bank Sta=4989.3,4993.3
Exp/Cntr=0.3,0.1

Type RM Length L Ch R = 1,1875,447,447,447
BEGIN DESCRIPTION:
Stream0036 3.0
END DESCRIPTION:
XS GIS Cut Line= 3
      1971875.01     13928124.98      1971775.00     13928325.00
      1971571.61     13928561.29
#Sta/Elev= 30
  4780.3 1655.33  4811.1 1652.63  4833.4 1646.18  4847.4 1640.35  4861.4 1636.09
  4883.7 1633.98  4925.9 1632.36  4967.6 1630.67  4981.6 1629.27  4990.0 1625.17
  4993.5 1624.23  4993.8 1623.73  4997.3 1623.73  4997.5 1624.23  5001.1 1626.37
  5007.2 1626.37  5011.1 1631.34  5017.7 1630.94  5025.3 1632.00  5039.6 1632.60
  5046.2 1634.68  5060.4 1637.29  5109.8 1642.72  5138.4 1645.13  5166.9 1645.64
  5216.3 1648.40  5238.2 1648.95  5281.0 1652.77  5287.6 1653.98  5315.7 1655.40
#Mann=4,-1,0
  4780.3     0.1       0  4925.9    0.07       0  4993.5    0.05       0
  4997.5    0.07       0
Bank Sta=4993.5,4997.5
Exp/Cntr=0.3,0.1

Type RM Length L Ch R = 1,1428,475,475,475
BEGIN DESCRIPTION:
Stream0036 2.0
END DESCRIPTION:
XS GIS Cut Line= 3
      1971630.13     13927912.87      1971425.00     13928125.00
      1971375.00     13928275.00
#Sta/Elev= 30
  4700.7 1652.87  4712.9 1650.71  4727.1 1649.11  4783.7 1645.13  4797.8 1643.13
  4804.8 1640.98  4818.9 1638.28  4826.1 1637.77  4847.7 1634.59  4860.0 1633.20
  4882.7 1630.08  4889.7 1628.33  4918.0 1625.29  4939.3 1624.68  4946.3 1623.63
  4953.5 1623.62  4987.4 1621.04  4992.8 1620.08  5006.3 1619.54  5016.9 1616.92
  5025.4 1616.63  5025.7 1616.13  5029.2 1616.13  5029.4 1616.63  5038.0 1620.65
  5048.5 1629.08  5059.0 1632.03  5090.7 1636.49  5143.4 1647.08  5153.9 1647.85
#Mann=7,-1,0
  4700.7    0.07       0  4847.7     0.1       0  4860.0   0.035       0
  4987.4    0.07       0  4992.8   0.035       0  5025.4   0.035       0
  5029.4   0.035       0
Bank Sta=5025.4,5029.4
Exp/Cntr=0.3,0.1

Type RM Length L Ch R = 1,953,614,614,614
BEGIN DESCRIPTION:
Stream0036 1.0
END DESCRIPTION:
XS GIS Cut Line= 3
      1971645.75     13927583.11      1971125.00     13927825.00
      1971036.75     13928035.35
#Sta/Elev= 30
  4430.1 1663.59  4486.1 1661.15  4538.5 1654.75  4629.4 1649.81  4635.6 1646.25
  4673.5 1645.97  4772.7 1640.86  4844.9 1633.33  4860.9 1630.01  4875.6 1625.57
  4883.0 1621.27  4905.1 1615.35  4944.3 1611.42  4972.7 1611.59  4982.2 1609.55
  4988.1 1606.05  4988.3 1605.55  4992.1 1606.05  4995.6 1609.71  5001.5 1610.85
  5026.0 1611.30  5048.1 1616.17  5058.5 1614.53  5080.2 1618.53  5095.6 1619.28
  5119.4 1622.77  5155.4 1623.85  5166.9 1624.30  5172.3 1623.13  5232.4 1625.06
#Mann=5,-1,0
  4430.1    0.07       0  4844.9     0.1       0  4988.1   0.035       0
  4992.1     0.1       0  5155.4     0.1       0
Bank Sta=4988.1,4992.1
Exp/Cntr=0.3,0.1

Type RM Length L Ch R = 1,339,180,180,180
BEGIN DESCRIPTION:
Stream0036 0.0
END DESCRIPTION:
XS GIS Cut Line= 3
      1970984.23     13926977.55      1970860.33     13927510.12
      1970892.93     13927948.12
#Sta/Elev= 30
  4619.2 1603.34  4677.5 1604.31  4780.9 1604.69  4873.3 1606.58  4883.5 1605.94
  4893.8 1603.87  4914.3 1603.58  4951.4 1600.96  4986.0 1596.07  4994.5 1591.01
  4994.7 1590.51  4998.5 1591.01  5006.7 1592.86  5017.0 1598.37  5033.7 1602.79
  5058.1 1605.54  5109.4 1608.09  5118.9 1609.13  5124.1 1608.48  5129.9 1609.48
  5211.0 1612.08  5281.2 1612.50  5311.3 1613.14  5321.3 1614.26  5354.6 1614.36
  5421.6 1614.59  5433.8 1615.44  5481.7 1616.36  5511.8 1616.23  5605.2 1617.80
#Mann=5,-1,0
  4619.2   0.035       0  4951.4     0.1       0  4994.5    0.05       0
  4998.5     0.1       0  5354.6   0.035       0
Bank Sta=4994.5,4998.5
Exp/Cntr=0.3,0.1

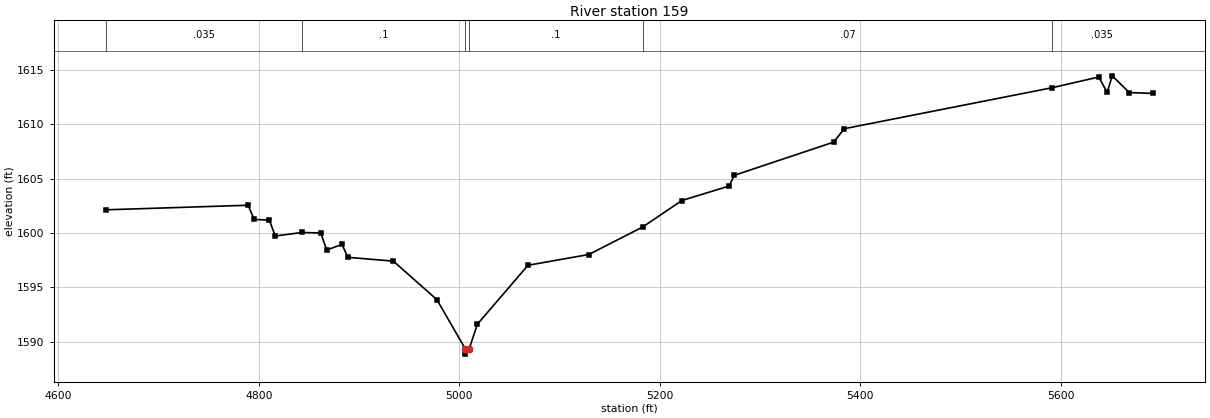
Type RM Length L Ch R = 1,159,0,0,0
BEGIN DESCRIPTION:
Stream0036 0.2
END DESCRIPTION:
XS GIS Cut Line= 4
      1970939.22     13926923.86      1970775.06     13927176.19
      1970746.39     13927370.25      1970847.88     13927908.27
#Sta/Elev= 30
  4647.4 1602.14  4789.3 1602.56  4795.3 1601.25  4810.4 1601.20  4816.4 1599.73
  4843.2 1600.06  4861.8 1600.00  4867.7 1598.44  4882.9 1598.96  4888.8 1597.77
  4934.2 1597.42  4977.6 1593.88  5005.9 1589.37  5006.1 1588.87  5009.9 1589.37
  5018.0 1591.62  5068.5 1597.04  5129.2 1598.03  5183.3 1600.58  5221.9 1602.99
  5269.2 1604.33  5274.3 1605.31  5373.3 1608.36  5384.2 1609.60  5591.0 1613.36
  5637.9 1614.35  5646.3 1612.94  5651.4 1614.46  5668.4 1612.92  5692.1 1612.84
#Mann=6,-1,0
  4647.4   0.035       0  4843.2     0.1       0  5005.9    0.05       0
  5009.9     0.1       0  5183.3    0.07       0  5591.0   0.035       0
Bank Sta=5005.9,5009.9
Exp/Cntr=0.3,0.1

Chan Stop Cuts=-1