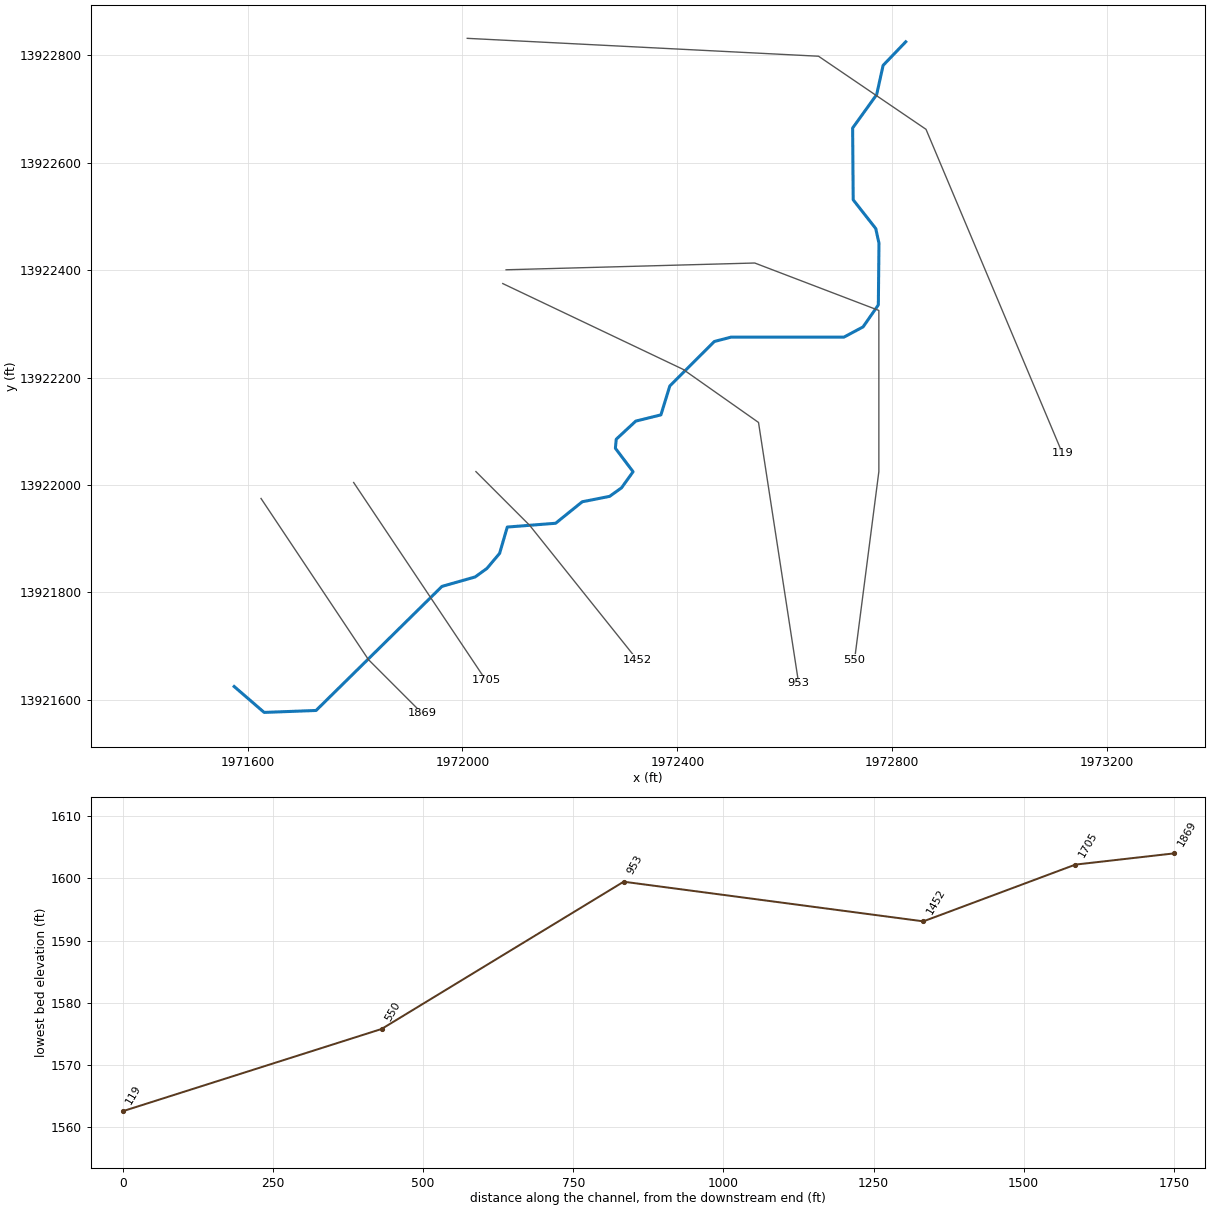
--- Stream0037.prj (project) ---

Proj Title=Stream0037 Base Level Engineering
Current Plan=p01
Default Exp/Contr=0.3,0.1
English Units
Geom File=g01
Flow File=f01
Plan File=p01
BEGIN DESCRIPTION:
Stream0037
END DESCRIPTION:

--- Stream0037.p01 (plan) ---

Plan Title=Multiple Run
Short Identifier=Multiple
Geom File=g01
Flow File=f01
Subcritical Flow
K Sum by GR= 0
Std Step Tol= 0.01
Critical Tol= 0.01
Num of Std Step Trials= 20
Max Error Tol= 0.3
Flow Tol Ratio= 0.001
Split Flow NTrial= 30
Split Flow Tol= 0.02
Split Flow Ratio= 0.02
Log Output Level= 0
Friction Slope Method= 1
Unsteady Friction Slope Method= 2
Unsteady Bridges Friction Slope Method= 1
Parabolic Critical Depth
Global Vel Dist=  1 , 1 , 1
Global Log Level= 0
CheckData=True
Encroach Param= -1, 0, 0, 0
BEGIN DESCRIPTION:
Multiple Run
END DESCRIPTION:

--- Stream0037.f01 (steady flow) ---

Flow Title=Multiple
Number of Profiles=7
Profile Names=10-year,25-year,50-year,1pct_min,100-year,1pct_plu,500-year
River Rch & RM= Stream0037,Reach-1,1869
     449     738    1007     670    1337    2667    2329
Boundary for River Rch & Prof#=Stream0037,Reach-1,1
Up Type=0
Dn Type=3
Dn Slope=0.005
Boundary for River Rch & Prof#=Stream0037,Reach-1,2
Up Type=0
Dn Type=3
Dn Slope=0.005
Boundary for River Rch & Prof#=Stream0037,Reach-1,3
Up Type=0
Dn Type=3
Dn Slope=0.005
Boundary for River Rch & Prof#=Stream0037,Reach-1,4
Up Type=0
Dn Type=3
Dn Slope=0.005
Boundary for River Rch & Prof#=Stream0037,Reach-1,5
Up Type=0
Dn Type=3
Dn Slope=0.005
Boundary for River Rch & Prof#=Stream0037,Reach-1,6
Up Type=0
Dn Type=3
Dn Slope=0.005
Boundary for River Rch & Prof#=Stream0037,Reach-1,7
Up Type=0
Dn Type=3
Dn Slope=0.005

--- Stream0037.g01 (geometry) ---

Geom Title=Existing Conditions

River Reach=Stream0037,Reach-1
Reach XY= 30
      1971575.00     13921625.00      1971630.84     13921576.77
      1971727.44     13921580.39      1971961.80     13921811.36
      1972023.55     13921828.92      1972045.43     13921844.74
      1972069.09     13921872.85      1972083.35     13921921.81
      1972173.35     13921928.86      1972222.88     13921968.86
      1972273.83     13921978.94      1972295.99     13921994.78
      1972317.52     13922024.80      1972284.58     13922068.46
      1972286.17     13922085.29      1972322.50     13922119.01
      1972369.32     13922130.62      1972385.88     13922184.44
      1972468.79     13922267.20      1972499.87     13922275.30
      1972709.98     13922275.32      1972745.66     13922294.40
      1972774.04     13922335.27      1972775.23     13922450.07
      1972769.26     13922477.33      1972727.25     13922530.94
      1972726.18     13922664.50      1972770.92     13922726.69
      1972782.91     13922781.15      1972825.00     13922825.00

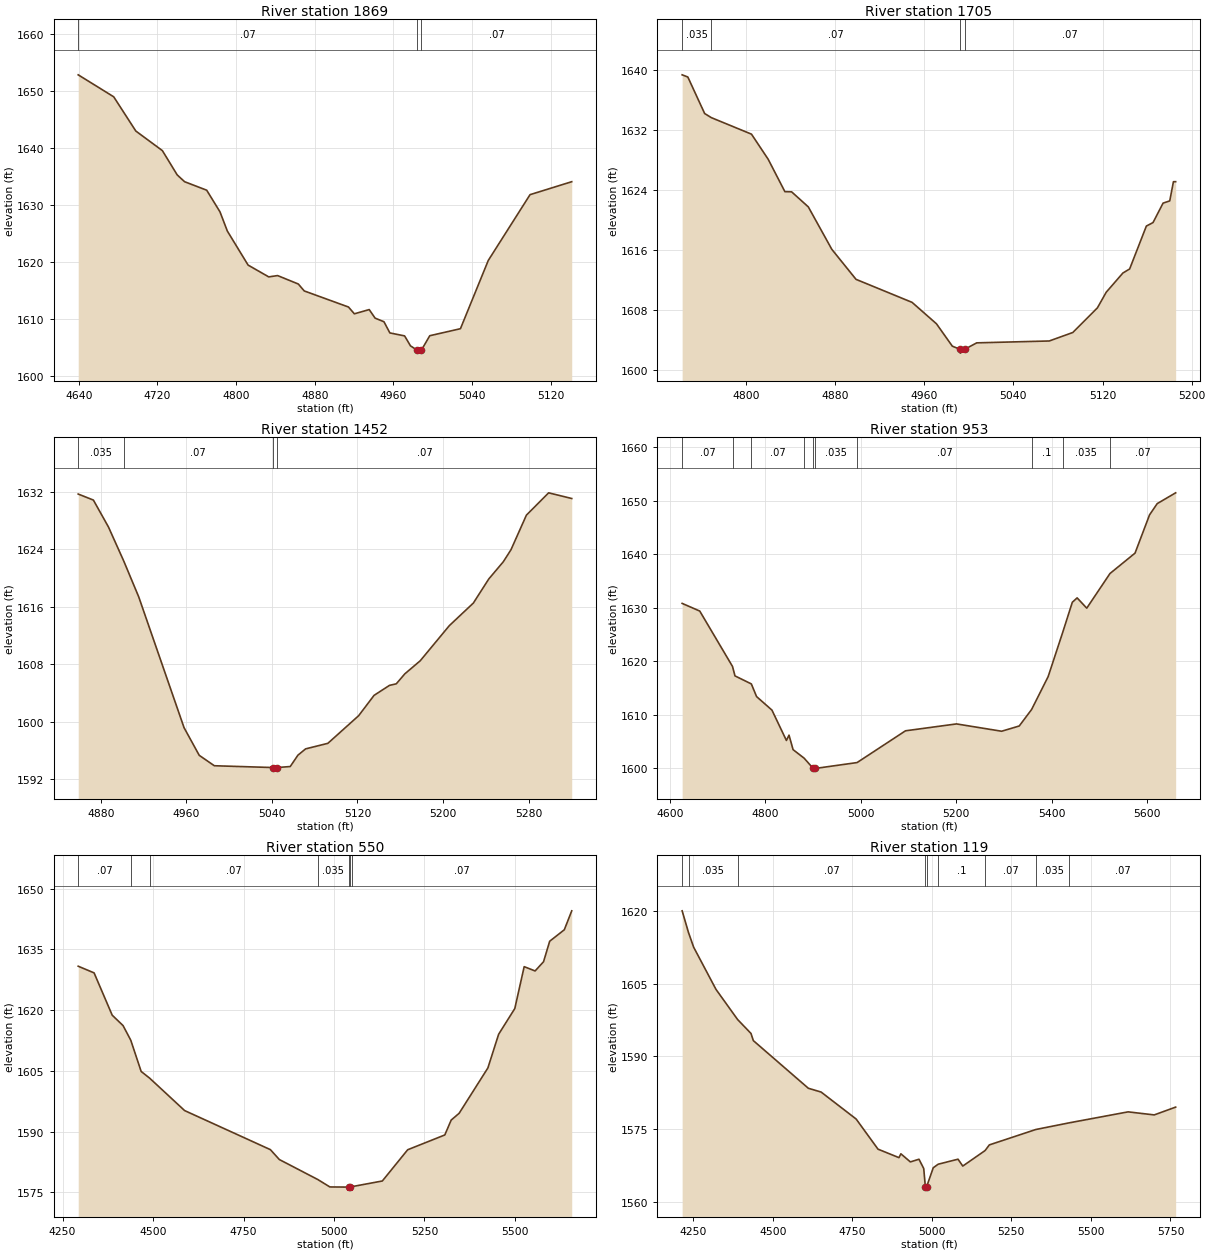
Type RM Length L Ch R = 1,1869,164,164,164
BEGIN DESCRIPTION:
Stream0037 4.0
END DESCRIPTION:
XS GIS Cut Line= 3
      1971625.00     13921975.01      1971825.00     13921675.00
      1971925.01     13921574.99
#Sta/Elev= 30
  4639.4 1652.78  4675.5 1648.93  4698.0 1642.93  4725.0 1639.50  4740.1 1635.24
  4747.6 1634.05  4770.1 1632.56  4783.6 1628.77  4791.1 1625.40  4812.2 1619.44
  4833.2 1617.37  4842.2 1617.60  4863.3 1616.12  4869.3 1614.91  4914.3 1612.09
  4920.3 1610.90  4935.4 1611.64  4941.4 1610.14  4950.4 1609.51  4956.4 1607.55
  4971.4 1607.03  4977.4 1605.28  4984.4 1604.51  4984.7 1604.01  4988.4 1604.51
  4997.0 1607.06  5028.2 1608.29  5056.5 1620.25  5099.0 1631.78  5141.4 1634.05
#Mann=3,-1,0
  4639.4    0.07       0  4984.4    0.05       0  4988.4    0.07       0
Bank Sta=4984.4,4988.4
Exp/Cntr=0.3,0.1

Type RM Length L Ch R = 1,1705,253,253,253
BEGIN DESCRIPTION:
Mapping XS 3fb6db2d
END DESCRIPTION:
XS GIS Cut Line= 2
      1971797.42     13922004.70      1972043.59     13921636.63
#Sta/Elev= 30
  4742.8 1639.32  4747.9 1639.03  4763.0 1634.16  4769.0 1633.61  4805.0 1631.41
  4820.0 1628.06  4835.0 1623.74  4841.0 1623.72  4856.0 1621.71  4877.1 1616.05
  4898.8 1612.05  4949.1 1608.98  4971.0 1606.12  4985.2 1603.14  4992.2 1602.71
  4992.4 1602.21  4996.2 1602.71  5007.1 1603.58  5072.2 1603.83  5093.3 1604.96
  5115.4 1608.25  5123.3 1610.33  5138.3 1612.90  5144.3 1613.43  5159.3 1619.15
  5165.3 1619.62  5174.3 1622.21  5180.3 1622.51  5183.6 1625.07  5185.6 1625.07
#Mann=4,-1,0
  4742.8   0.035       0  4769.0    0.07       0  4992.2    0.05       0
  4996.2    0.07       0
Bank Sta=4992.2,4996.2
Exp/Cntr=0.3,0.1

Type RM Length L Ch R = 1,1452,499,499,499
BEGIN DESCRIPTION:
Stream0037 3.0
END DESCRIPTION:
XS GIS Cut Line= 3
      1972024.98     13922025.02      1972125.00     13921925.00
      1972325.00     13921675.00
#Sta/Elev= 30
  4858.8 1631.68  4873.0 1630.84  4887.1 1627.09  4901.3 1622.38  4915.4 1617.36
  4957.8 1599.14  4972.0 1595.29  4986.1 1593.84  5040.7 1593.59  5040.9 1593.09
  5044.4 1593.09  5044.7 1593.59  5057.1 1593.73  5064.3 1595.31  5071.5 1596.19
  5092.3 1596.96  5121.1 1600.81  5135.5 1603.64  5149.9 1605.03  5156.3 1605.25
  5164.3 1606.64  5178.7 1608.46  5205.9 1613.35  5228.4 1616.50  5242.8 1619.85
  5256.4 1622.25  5263.6 1623.93  5278.0 1628.74  5298.8 1631.85  5320.4 1631.06
#Mann=4,-1,0
  4858.8   0.035       0  4901.3    0.07       0  5040.7    0.05       0
  5044.7    0.07       0
Bank Sta=5040.7,5044.7
Exp/Cntr=0.3,0.1

Type RM Length L Ch R = 1,953,403,403,403
BEGIN DESCRIPTION:
Stream0037 2.0
END DESCRIPTION:
XS GIS Cut Line= 4
      1972074.96     13922375.02      1972410.38     13922215.46
      1972551.00     13922116.50      1972625.73     13921630.81
#Sta/Elev= 30
  4625.3 1630.83  4662.2 1629.40  4730.9 1619.04  4736.1 1617.27  4770.4 1615.77
  4781.3 1613.41  4813.6 1610.87  4843.9 1605.20  4849.4 1606.19  4857.9 1603.48
  4881.2 1601.87  4900.2 1599.96  4900.4 1599.46  4904.2 1599.96  4992.1 1601.06
  5093.6 1607.00  5200.6 1608.29  5295.2 1606.92  5332.1 1607.90  5358.0 1610.98
  5392.8 1617.15  5423.4 1625.45  5443.4 1631.04  5453.5 1631.86  5473.7 1629.94
  5522.4 1636.42  5574.9 1640.23  5605.3 1647.38  5621.4 1649.49  5660.1 1651.51
#Mann=10,-1,0
  4625.3    0.07       0  4730.9   0.035       0  4770.4    0.07       0
  4881.2   0.035       0  4900.2    0.05       0  4904.2   0.035       0
  4992.1    0.07       0  5358.0     0.1       0  5423.4   0.035       0
  5522.4    0.07       0
Bank Sta=4900.2,4904.2
Exp/Cntr=0.3,0.1

Type RM Length L Ch R = 1,550,431,431,431
BEGIN DESCRIPTION:
Stream0037 1.0
END DESCRIPTION:
XS GIS Cut Line= 5
      1972081.13     13922400.69      1972543.98     13922413.29
      1972775.00     13922325.00      1972775.00     13922025.00
      1972729.77     13921674.65
#Sta/Elev= 30
  4293.3 1630.84  4337.2 1629.19  4387.2 1618.75  4417.2 1616.18  4438.6 1612.55
  4467.2 1604.85  4490.6 1603.20  4587.3 1595.19  4824.3 1585.54  4849.0 1583.10
  4955.3 1578.16  4988.6 1576.33  5041.6 1576.29  5041.9 1575.79  5045.6 1576.29
  5049.9 1576.41  5133.6 1577.80  5203.6 1585.51  5306.2 1589.17  5323.8 1592.84
  5345.9 1594.53  5425.2 1605.71  5454.9 1614.03  5499.6 1620.39  5525.5 1630.73
  5555.7 1629.67  5579.0 1631.95  5596.0 1637.01  5636.4 1639.84  5656.9 1644.52
#Mann=7,-1,0
  4293.3    0.07       0  4438.6   0.035       0  4490.6    0.07       0
  4955.3   0.035       0  5041.6   0.035       0  5045.6   0.035       0
  5049.9    0.07       0
Bank Sta=5041.6,5045.6
Exp/Cntr=0.3,0.1

Type RM Length L Ch R = 1,119,0,0,0
BEGIN DESCRIPTION:
Stream0037 0.0
END DESCRIPTION:
XS GIS Cut Line= 4
      1972008.88     13922831.50      1972662.73     13922798.19
      1972862.77     13922662.16      1973116.67     13922059.14
#Sta/Elev= 30
  4215.4 1620.02  4235.4 1615.53  4251.6 1612.51  4321.7 1603.81  4389.6 1597.59
  4431.8 1594.70  4439.1 1593.23  4612.0 1583.39  4652.1 1582.61  4762.2 1577.04
  4830.9 1570.82  4896.7 1569.07  4902.8 1569.86  4932.6 1568.19  4959.7 1568.74
  4974.6 1566.82  4979.7 1563.07  4979.9 1562.57  4983.7 1563.07  5004.5 1566.98
  5019.8 1567.71  5082.4 1568.75  5097.3 1567.33  5167.2 1570.52  5180.8 1571.70
  5326.9 1574.88  5432.2 1576.26  5616.9 1578.52  5698.9 1577.89  5766.3 1579.50
#Mann=9,-1,0
  4215.4    0.07       0  4235.4   0.035       0  4389.6    0.07       0
  4979.7    0.05       0  4983.7    0.07       0  5019.8     0.1       0
  5167.2    0.07       0  5326.9   0.035       0  5432.2    0.07       0
Bank Sta=4979.7,4983.7
Exp/Cntr=0.3,0.1

Chan Stop Cuts=-1