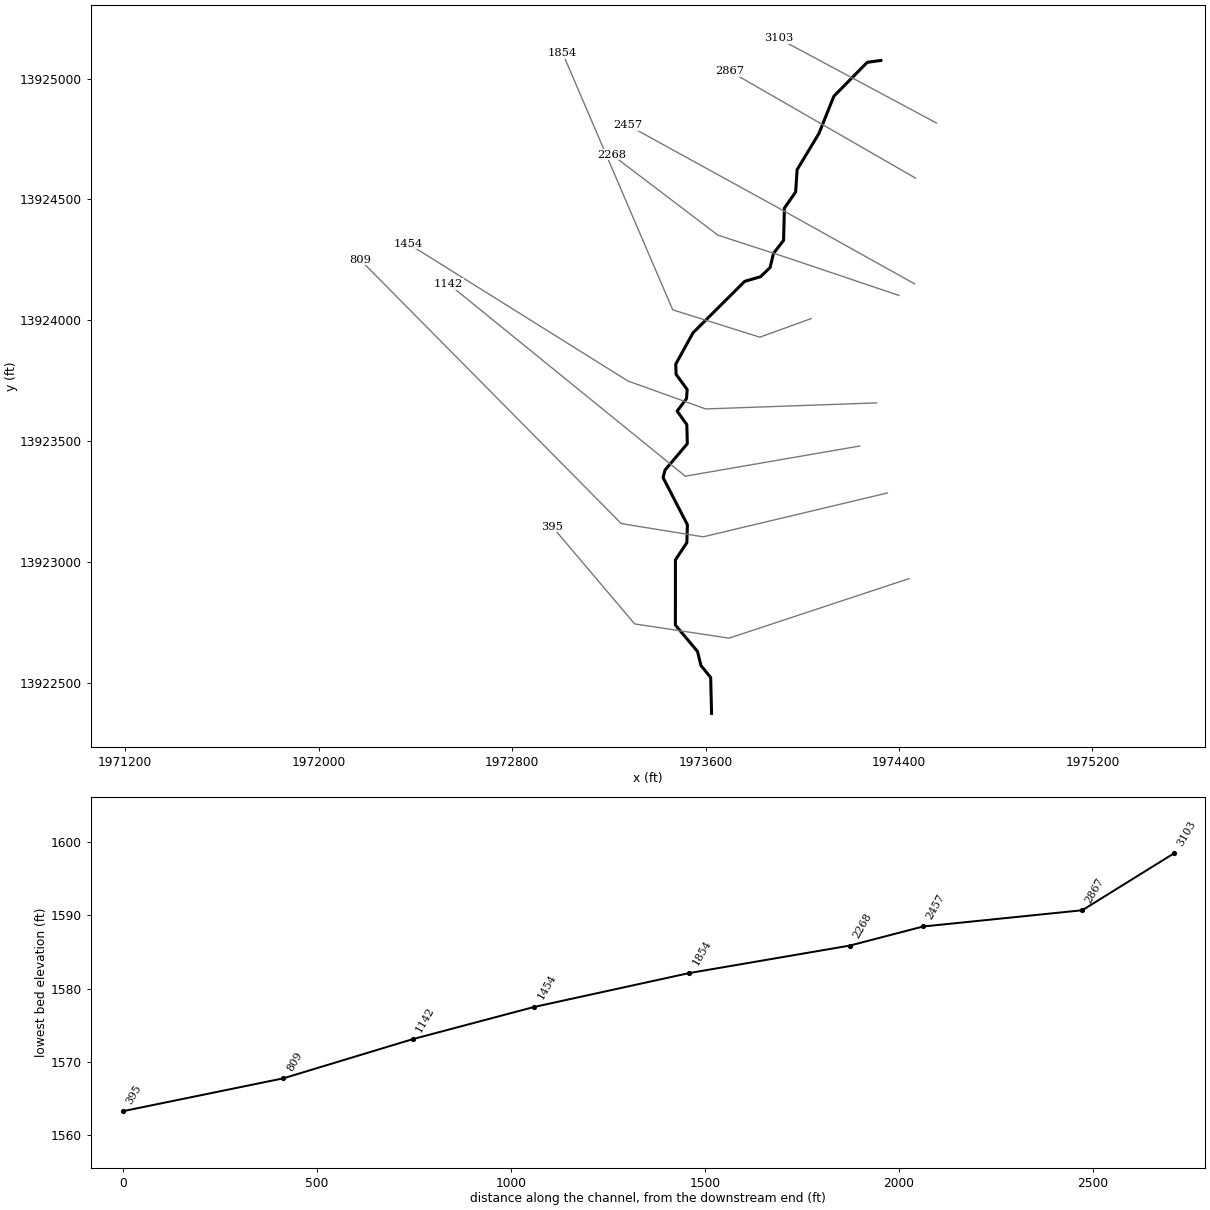
--- Stream0038.prj (project) ---

Proj Title=Stream0038 Base Level Engineering
Current Plan=p01
Default Exp/Contr=0.3,0.1
English Units
Geom File=g01
Flow File=f01
Plan File=p01
BEGIN DESCRIPTION:
Stream0038
END DESCRIPTION:

--- Stream0038.p01 (plan) ---

Plan Title=Multiple Run
Short Identifier=Multiple
Geom File=g01
Flow File=f01
Subcritical Flow
K Sum by GR= 0
Std Step Tol= 0.01
Critical Tol= 0.01
Num of Std Step Trials= 20
Max Error Tol= 0.3
Flow Tol Ratio= 0.001
Split Flow NTrial= 30
Split Flow Tol= 0.02
Split Flow Ratio= 0.02
Log Output Level= 0
Friction Slope Method= 1
Unsteady Friction Slope Method= 2
Unsteady Bridges Friction Slope Method= 1
Parabolic Critical Depth
Global Vel Dist=  1 , 1 , 1
Global Log Level= 0
CheckData=True
Encroach Param= -1, 0, 0, 0
BEGIN DESCRIPTION:
Multiple Run
END DESCRIPTION:

--- Stream0038.f01 (steady flow) ---

Flow Title=Multiple
Number of Profiles=7
Profile Names=10-year,25-year,50-year,1pct_min,100-year,1pct_plu,500-year
River Rch & RM= Stream0038,Reach-1,3103
    1018    1750    2455    1672    3336    6657    6111
Boundary for River Rch & Prof#=Stream0038,Reach-1,1
Up Type=0
Dn Type=3
Dn Slope=0.005
Boundary for River Rch & Prof#=Stream0038,Reach-1,2
Up Type=0
Dn Type=3
Dn Slope=0.005
Boundary for River Rch & Prof#=Stream0038,Reach-1,3
Up Type=0
Dn Type=3
Dn Slope=0.005
Boundary for River Rch & Prof#=Stream0038,Reach-1,4
Up Type=0
Dn Type=3
Dn Slope=0.005
Boundary for River Rch & Prof#=Stream0038,Reach-1,5
Up Type=0
Dn Type=3
Dn Slope=0.005
Boundary for River Rch & Prof#=Stream0038,Reach-1,6
Up Type=0
Dn Type=3
Dn Slope=0.005
Boundary for River Rch & Prof#=Stream0038,Reach-1,7
Up Type=0
Dn Type=3
Dn Slope=0.005

--- Stream0038.g01 (geometry) ---

Geom Title=Existing Conditions

River Reach=Stream0038,Reach-1
Reach XY= 30
      1974325.00     13925075.00      1974268.79     13925067.24
      1974130.83     13924927.30      1974068.92     13924772.80
      1973978.83     13924623.42      1973972.64     13924530.98
      1973926.23     13924464.49      1973922.75     13924330.93
      1973881.15     13924277.15      1973866.98     13924218.66
      1973827.54     13924180.75      1973761.80     13924161.36
      1973548.01     13923948.47      1973476.80     13923818.89
      1973478.40     13923776.72      1973524.16     13923714.30
      1973521.39     13923676.64      1973482.60     13923625.01
      1973522.64     13923569.10      1973524.75     13923490.22
      1973432.50     13923381.05      1973424.50     13923350.03
      1973525.11     13923154.91      1973522.83     13923080.98
      1973475.52     13923009.78      1973475.39     13922740.16
      1973566.84     13922631.05      1973581.14     13922572.83
      1973621.28     13922523.46      1973625.00     13922375.00

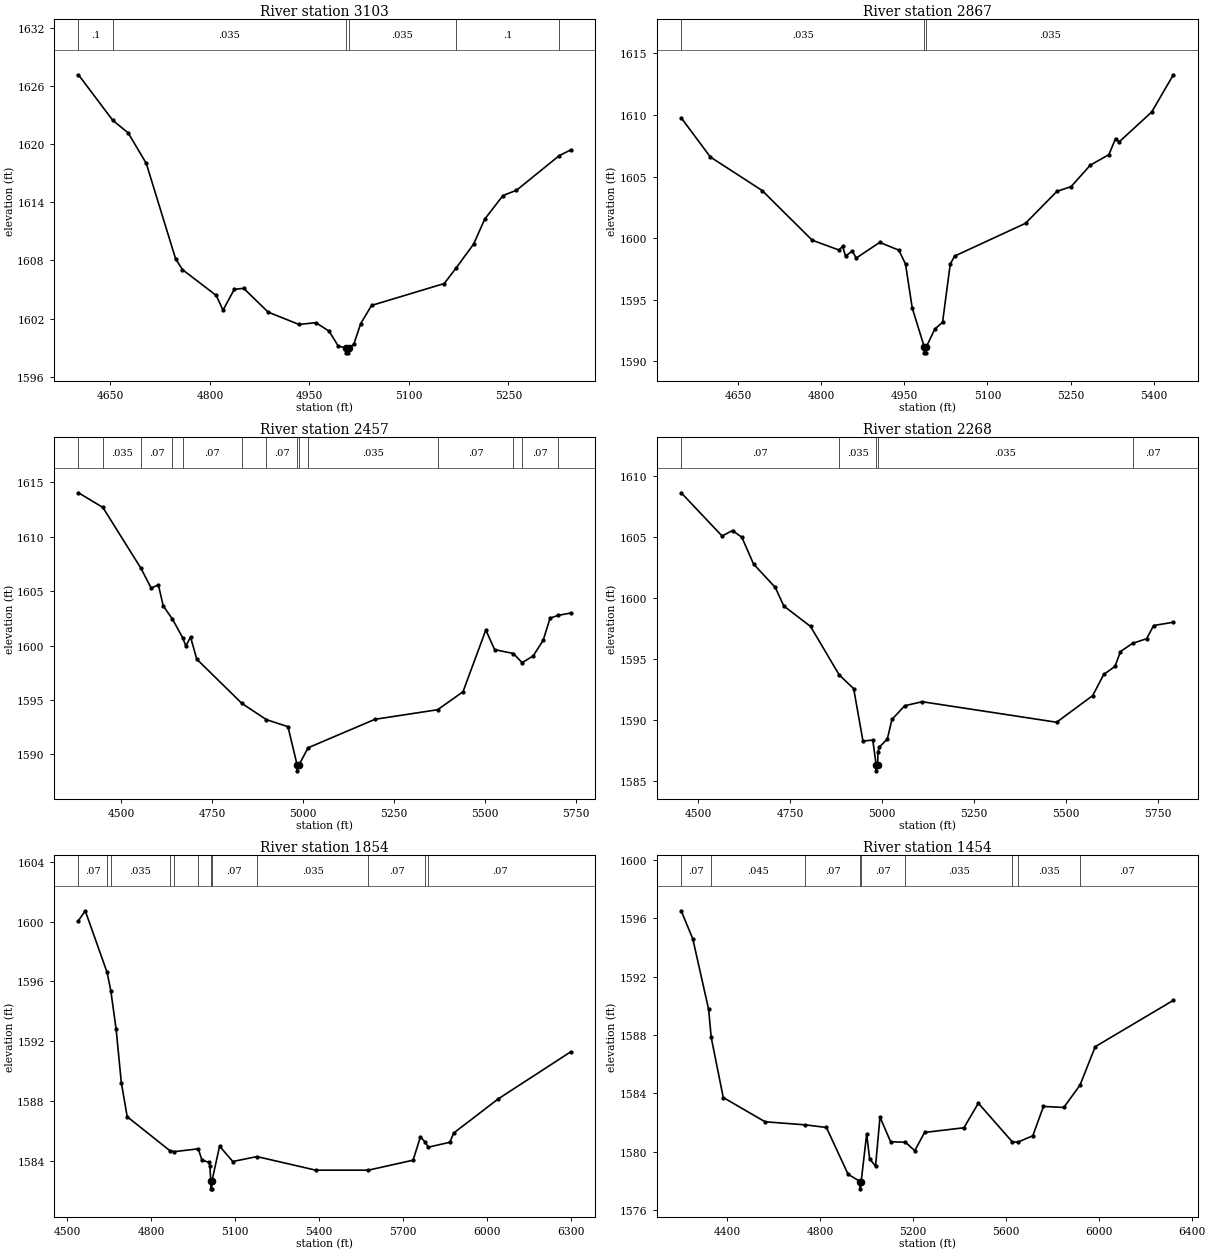
Type RM Length L Ch R = 1,3103,236,236,236
BEGIN DESCRIPTION:
DSTOUS237 4.0
END DESCRIPTION:
XS GIS Cut Line= 2
      1974555.11     13924816.26      1973901.06     13925166.45
#Sta/Elev= 30
  4601.8 1627.16  4653.5 1622.46  4676.8 1621.16  4704.0 1618.02  4748.2 1608.18
  4758.5 1607.06  4809.5 1604.39  4819.7 1602.87  4836.7 1605.02  4850.8 1605.13
  4887.8 1602.67  4934.2 1601.40  4959.7 1601.58  4979.6 1600.71  4993.3 1599.18
  5004.9 1598.97  5005.1 1598.47  5008.6 1598.47  5008.9 1598.97  5016.9 1599.36
  5027.3 1601.49  5043.6 1603.36  5153.2 1605.62  5170.7 1607.19  5197.4 1609.68
  5214.3 1612.27  5241.7 1614.70  5262.1 1615.24  5326.6 1618.82  5343.7 1619.40
#Mann=6,-1,0
  4601.8     0.1       0  4653.5   0.035       0  5004.9   0.035       0
  5008.9   0.035       0  5170.7     0.1       0  5326.6    0.07       0
Bank Sta=5004.9,5008.9
Exp/Cntr=0.3,0.1

Type RM Length L Ch R = 1,2867,410,410,410
BEGIN DESCRIPTION:
Mapping XS a40d1973
END DESCRIPTION:
XS GIS Cut Line= 2
      1974468.60     13924588.32      1973699.25     13925031.16
#Sta/Elev= 30
  4547.7 1609.77  4600.3 1606.59  4693.7 1603.87  4784.0 1599.84  4832.4 1599.04
  4838.8 1599.35  4844.1 1598.55  4856.3 1598.96  4863.4 1598.39  4905.8 1599.66
  4940.3 1599.03  4952.3 1597.91  4964.4 1594.35  4986.0 1591.20  4986.2 1590.70
  4989.7 1590.70  4990.0 1591.20  5005.3 1592.64  5019.1 1593.17  5033.0 1597.90
  5040.9 1598.55  5168.8 1601.21  5225.4 1603.80  5251.1 1604.19  5285.7 1605.93
  5319.2 1606.78  5331.2 1608.09  5337.6 1607.81  5396.4 1610.24  5435.4 1613.26
#Mann=3,-1,0
  4547.7   0.035       0  4986.0   0.035       0  4990.0   0.035       0
Bank Sta=4986,4990
Exp/Cntr=0.3,0.1

Type RM Length L Ch R = 1,2457,189,189,189
BEGIN DESCRIPTION:
DSTOUS237 3.0
END DESCRIPTION:
XS GIS Cut Line= 3
      1974464.22     13924151.34      1973920.92     13924454.37
      1973279.90     13924806.77
#Sta/Elev= 30
  4382.5 1614.05  4449.7 1612.70  4554.5 1607.10  4582.5 1605.28  4602.3 1605.59
  4615.6 1603.65  4640.8 1602.44  4669.5 1600.70  4677.8 1599.96  4690.8 1600.78
  4707.9 1598.75  4832.0 1594.68  4899.3 1593.19  4958.7 1592.54  4984.2 1588.98
  4984.4 1588.48  4988.2 1588.98  5014.1 1590.60  5198.1 1593.22  5370.3 1594.10
  5440.1 1595.75  5502.9 1601.43  5527.1 1599.63  5578.8 1599.27  5602.6 1598.43
  5633.3 1599.05  5660.7 1600.49  5679.6 1602.52  5701.0 1602.77  5736.1 1602.99
#Mann=14,-1,0
  4382.5    0.07       0  4449.7   0.035       0  4554.5    0.07       0
  4640.8   0.035       0  4669.5    0.07       0  4832.0   0.035       0
  4899.3    0.07       0  4984.2    0.05       0  4988.2    0.07       0
  5014.1   0.035       0  5370.3    0.07       0  5578.8   0.035       0
  5602.6    0.07       0  5701.0   0.035       0
Bank Sta=4984.2,4988.2
Exp/Cntr=0.3,0.1

Type RM Length L Ch R = 1,2268,414,414,414
BEGIN DESCRIPTION:
DSTOUS237 2.0
END DESCRIPTION:
XS GIS Cut Line= 4
      1974399.41     13924103.36      1973940.08     13924258.50
      1973651.37     13924352.49      1973213.26     13924685.09
#Sta/Elev= 30
  4453.5 1608.64  4564.7 1605.10  4593.2 1605.55  4618.6 1604.99  4650.2 1602.81
  4709.3 1600.89  4732.6 1599.37  4805.4 1597.69  4883.1 1593.73  4922.6 1592.60
  4947.9 1588.31  4974.6 1588.39  4983.7 1586.37  4984.0 1585.87  4987.7 1586.37
  4988.8 1587.39  4992.0 1587.80  5014.1 1588.47  5026.7 1590.08  5061.4 1591.20
  5108.8 1591.53  5474.6 1589.85  5572.6 1592.03  5602.7 1593.76  5633.4 1594.43
  5648.3 1595.64  5681.1 1596.31  5719.5 1596.69  5738.3 1597.77  5792.0 1598.04
#Mann=5,-1,0
  4453.5    0.07       0  4883.1   0.035       0  4983.7   0.035       0
  4987.7   0.035       0  5681.1    0.07       0
Bank Sta=4983.7,4987.7
Exp/Cntr=0.3,0.1

Type RM Length L Ch R = 1,1854,400,400,400
BEGIN DESCRIPTION:
DSTOUS237 1.0
END DESCRIPTION:
XS GIS Cut Line= 4
      1974036.59     13924007.53      1973824.59     13923930.68
      1973464.28     13924043.84      1973009.30     13925104.51
#Sta/Elev= 30
  4540.0 1600.07  4564.2 1600.73  4642.1 1596.61  4655.4 1595.39  4674.6 1592.78
  4693.0 1589.23  4714.0 1586.94  4866.2 1584.67  4882.0 1584.60  4967.8 1584.79
  4981.0 1584.03  5006.1 1583.89  5009.3 1583.65  5012.4 1582.61  5012.7 1582.11
  5016.2 1582.11  5016.4 1582.61  5043.9 1584.97  5091.0 1583.94  5177.4 1584.27
  5387.3 1583.36  5575.0 1583.36  5734.9 1584.03  5761.1 1585.60  5776.0 1585.28
  5789.3 1584.90  5866.5 1585.23  5879.3 1585.84  6039.4 1588.14  6297.3 1591.28
#Mann=12,-1,0
  4540.0    0.07       0  4642.1   0.045       0  4655.4   0.035       0
  4866.2    0.07       0  4882.0   0.035       0  4967.8    0.07       0
  5012.4    0.05       0  5016.4    0.07       0  5177.4   0.035       0
  5575.0    0.07       0  5776.0   0.035       0  5789.3    0.07       0
Bank Sta=5012.4,5016.4
Exp/Cntr=0.3,0.1

Type RM Length L Ch R = 1,1454,312,312,312
BEGIN DESCRIPTION:
Mapping XS 97c2a7a1
END DESCRIPTION:
XS GIS Cut Line= 4
      1974307.09     13923658.92      1973600.61     13923633.90
      1973279.29     13923749.41      1972370.62     13924317.29
#Sta/Elev= 30
  4200.9 1596.50  4251.0 1594.57  4319.1 1589.75  4330.3 1587.83  4382.1 1583.72
  4562.2 1582.06  4734.9 1581.85  4826.4 1581.67  4920.1 1578.46  4972.2 1577.97
  4972.4 1577.47  4976.2 1577.97  4999.8 1581.22  5012.6 1579.52  5038.1 1579.03
  5057.2 1582.38  5103.1 1580.69  5166.7 1580.66  5207.1 1580.08  5249.3 1581.33
  5418.7 1581.65  5480.9 1583.33  5627.4 1580.68  5651.4 1580.67  5715.4 1581.10
  5761.4 1583.11  5848.9 1583.04  5918.9 1584.57  5984.4 1587.20  6320.8 1590.37
#Mann=9,-1,0
  4200.9    0.07       0  4330.3   0.045       0  4734.9    0.07       0
  4972.2    0.05       0  4976.2    0.07       0  5166.7   0.035       0
  5627.4    0.07       0  5651.4   0.035       0  5918.9    0.07       0
Bank Sta=4972.2,4976.2
Exp/Cntr=0.3,0.1

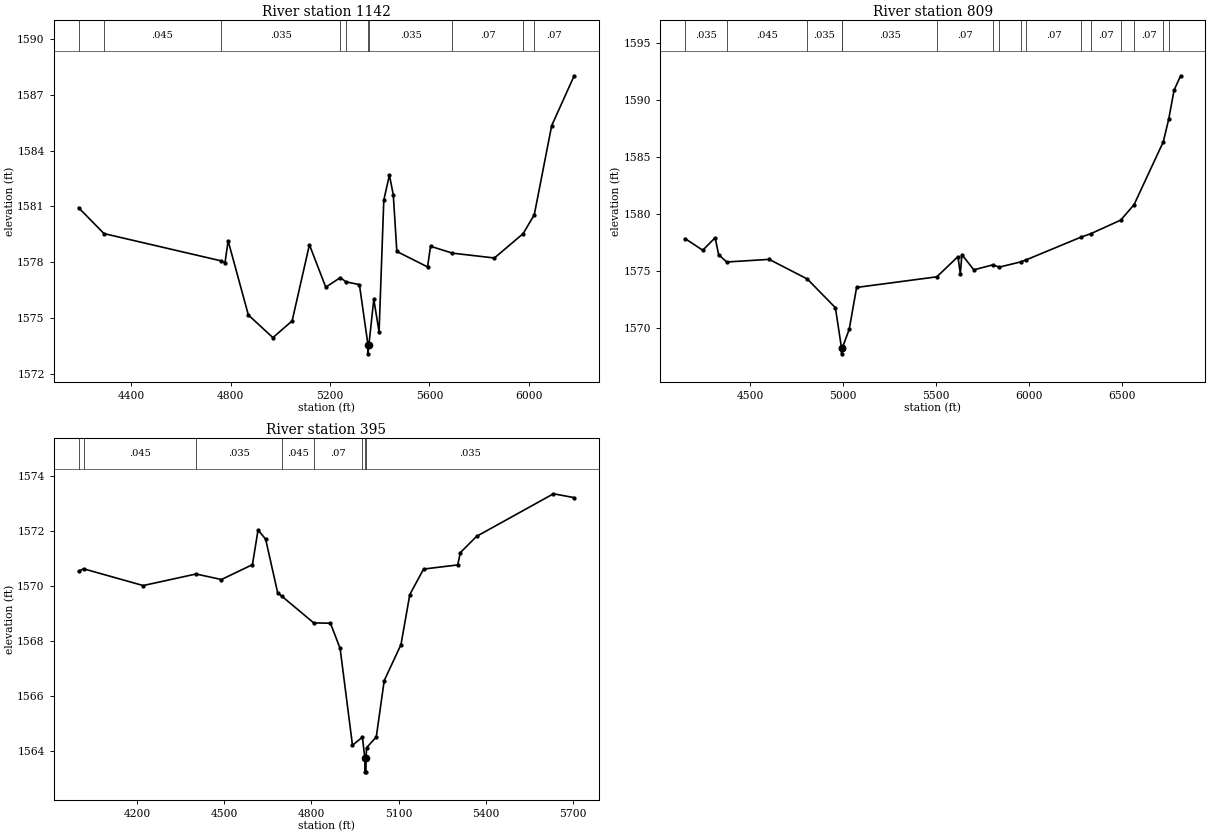
Type RM Length L Ch R = 1,1142,333,333,333
BEGIN DESCRIPTION:
DSTOUS237 0.1
END DESCRIPTION:
XS GIS Cut Line= 3
      1974237.65     13923480.57      1973516.50     13923355.78
      1972537.44     13924150.87
#Sta/Elev= 30
  4189.0 1580.93  4291.1 1579.54  4760.7 1578.08  4777.8 1577.98  4790.3 1579.15
  4871.6 1575.17  4970.4 1573.95  5047.7 1574.85  5117.3 1578.94  5183.0 1576.66
  5241.8 1577.18  5263.5 1576.95  5318.3 1576.80  5352.6 1573.58  5352.8 1573.08
  5356.6 1573.58  5376.2 1576.01  5397.4 1574.26  5416.4 1581.34  5439.0 1582.68
  5454.5 1581.63  5468.9 1578.58  5592.5 1577.75  5604.3 1578.86  5692.4 1578.49
  5861.3 1578.23  5976.9 1579.54  6021.6 1580.55  6091.6 1585.34  6182.1 1588.02
#Mann=10,-1,0
  4189.0    0.07       0  4291.1   0.045       0  4760.7   0.035       0
  5241.8    0.07       0  5263.5   0.035       0  5352.6   0.035       0
  5356.6   0.035       0  5692.4    0.07       0  5976.9   0.035       0
  6021.6    0.07       0
Bank Sta=5352.6,5356.6
Exp/Cntr=0.3,0.1

Type RM Length L Ch R = 1,809,414,414,414
BEGIN DESCRIPTION:
Mapping XS 6fe50d34
END DESCRIPTION:
XS GIS Cut Line= 4
      1974352.13     13923286.34      1973590.11     13923105.01
      1973251.75     13923159.76      1972171.58     13924251.29
#Sta/Elev= 30
  4151.5 1577.83  4246.4 1576.81  4313.0 1577.91  4331.5 1576.42  4375.3 1575.78
  4602.9 1576.01  4807.9 1574.29  4958.9 1571.77  4991.7 1568.23  4991.9 1567.73
  4995.7 1568.23  5033.2 1569.89  5072.7 1573.55  5503.7 1574.48  5617.0 1576.25
  5629.9 1574.75  5638.3 1576.43  5702.3 1575.09  5804.3 1575.53  5839.3 1575.33
  5954.6 1575.79  5984.1 1575.97  6278.0 1577.96  6330.7 1578.26  6491.4 1579.45
  6563.2 1580.81  6720.0 1586.31  6749.1 1588.30  6777.9 1590.84  6813.2 1592.10
#Mann=16,-1,0
  4151.5   0.035       0  4375.3   0.045       0  4807.9   0.035       0
  4991.7   0.035       0  4995.7   0.035       0  5503.7    0.07       0
  5804.3   0.035       0  5839.3    0.07       0  5954.6   0.035       0
  5984.1    0.07       0  6278.0   0.035       0  6330.7    0.07       0
  6491.4   0.035       0  6563.2    0.07       0  6720.0   0.035       0
  6749.1    0.07       0
Bank Sta=4991.7,4995.7
Exp/Cntr=0.3,0.1

Type RM Length L Ch R = 1,395,0,0,0
BEGIN DESCRIPTION:
DSTOUS237 0.0
END DESCRIPTION:
XS GIS Cut Line= 4
      1974441.78     13922932.33      1973697.40     13922686.06
      1973307.00     13922744.89      1972966.99     13923146.41
#Sta/Elev= 30
  3999.3 1570.53  4016.1 1570.62  4221.3 1570.01  4403.1 1570.43  4490.7 1570.23
  4597.3 1570.77  4616.6 1572.03  4642.7 1571.70  4684.3 1569.74  4698.7 1569.62
  4808.3 1568.65  4865.7 1568.64  4899.0 1567.72  4941.5 1564.20  4975.6 1564.49
  4984.1 1563.73  4984.3 1563.23  4987.9 1563.23  4988.2 1563.73  4990.1 1564.11
  5023.4 1564.50  5050.7 1566.55  5108.4 1567.86  5138.7 1569.68  5186.2 1570.61
  5303.5 1570.76  5312.8 1571.21  5368.5 1571.80  5633.1 1573.35  5704.3 1573.21
#Mann=8,-1,0
  3999.3   0.035       0  4016.1   0.045       0  4403.1   0.035       0
  4698.7   0.045       0  4808.3    0.07       0  4975.6   0.035       0
  4984.1   0.035       0  4988.2   0.035       0
Bank Sta=4984.1,4988.2
Exp/Cntr=0.3,0.1

Chan Stop Cuts=-1