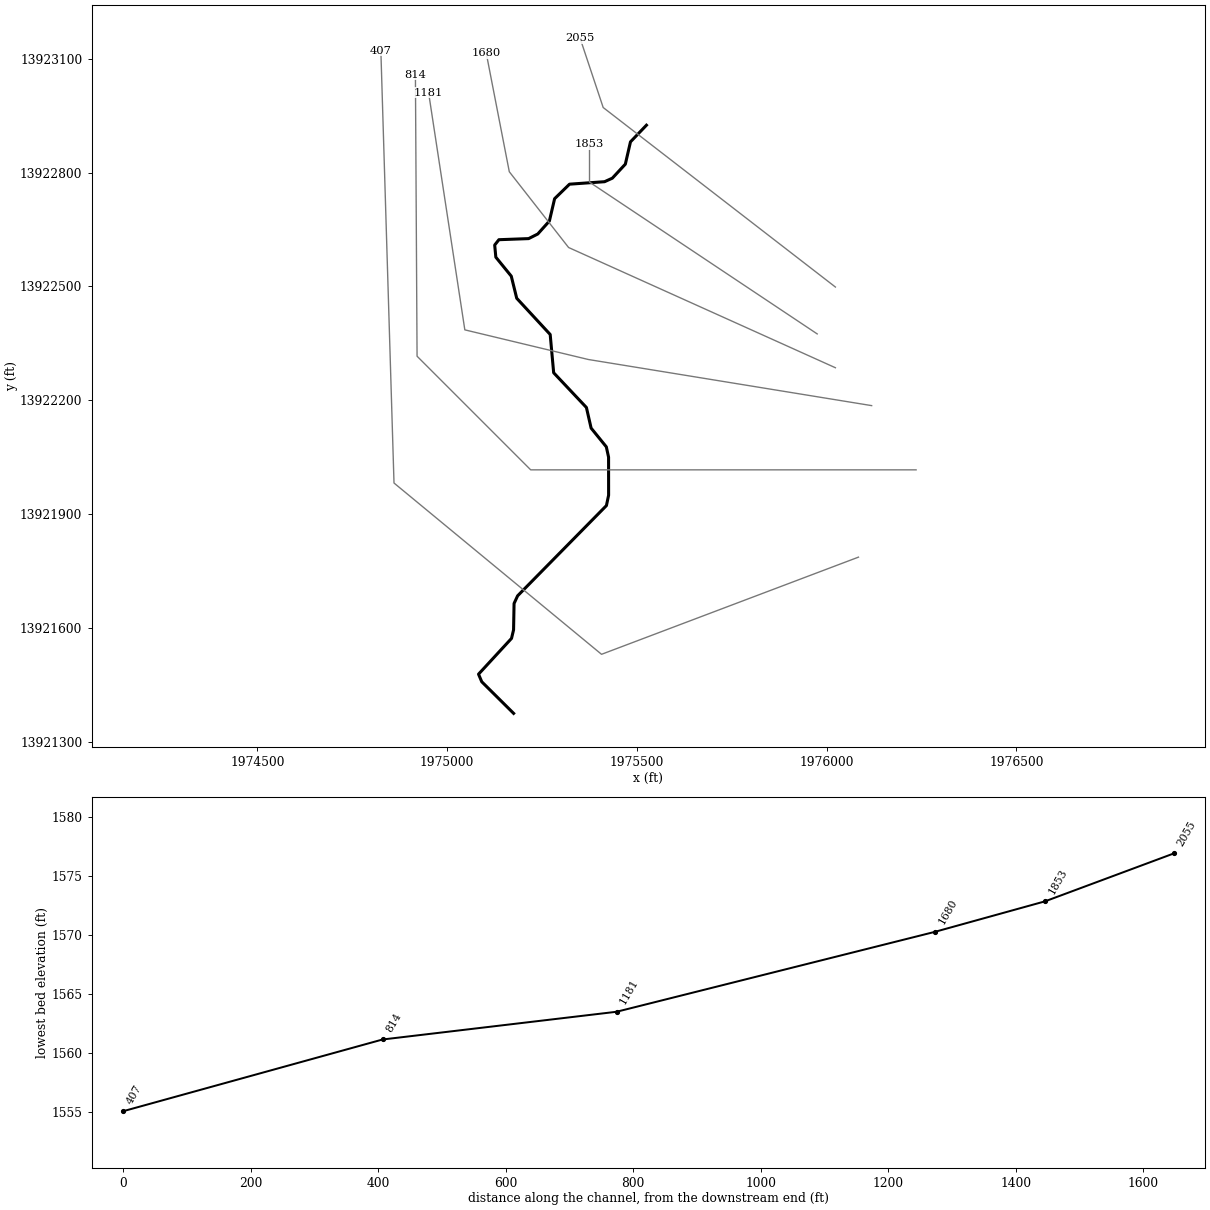
--- Stream0039.prj (project) ---

Proj Title=Stream0039 Base Level Engineering
Current Plan=p01
Default Exp/Contr=0.3,0.1
English Units
Geom File=g01
Flow File=f01
Plan File=p01
Y Axis Title=Elevation
X Axis Title(PF)=Main Channel Distance
X Axis Title(XS)=Station
BEGIN DESCRIPTION:
Stream0039
END DESCRIPTION:
DSS Export Rating Curves= 0
DSS Export Rating Curve Sorted= 0
DSS Export Volume Flow Curves= 0
DXF OffsetX= 0
DXF OffsetY= 0
DXF ScaleX= 1
DXF ScaleY= 10

--- Stream0039.p01 (plan) ---

Plan Title=Multiple Run
Short Identifier=Multiple
Geom File=g01
Flow File=f01
Subcritical Flow
K Sum by GR= 0
Std Step Tol= 0.01
Critical Tol= 0.01
Num of Std Step Trials= 20
Max Error Tol= 0.3
Flow Tol Ratio= 0.001
Split Flow NTrial= 30
Split Flow Tol= 0.02
Split Flow Ratio= 0.02
Log Output Level= 0
Friction Slope Method= 1
Unsteady Friction Slope Method= 2
Unsteady Bridges Friction Slope Method= 1
Parabolic Critical Depth
Global Vel Dist=  1 , 1 , 1
Global Log Level= 0
CheckData=True
Encroach Param= -1, 0, 0, 0
BEGIN DESCRIPTION:
Multiple Run
END DESCRIPTION:

--- Stream0039.f01 (steady flow) ---

Flow Title=Multiple
Number of Profiles=7
Profile Names=10-year,25-year,50-year,1pct_min,100-year,1pct_plu,500-year
River Rch & RM= Stream0039,Reach-1,2055
     424     691     936     618    1233    2461    2117
Boundary for River Rch & Prof#=Stream0039,Reach-1,1
Up Type=0
Dn Type=3
Dn Slope=0.005
Boundary for River Rch & Prof#=Stream0039,Reach-1,2
Up Type=0
Dn Type=3
Dn Slope=0.005
Boundary for River Rch & Prof#=Stream0039,Reach-1,3
Up Type=0
Dn Type=3
Dn Slope=0.005
Boundary for River Rch & Prof#=Stream0039,Reach-1,4
Up Type=0
Dn Type=3
Dn Slope=0.005
Boundary for River Rch & Prof#=Stream0039,Reach-1,5
Up Type=0
Dn Type=3
Dn Slope=0.005
Boundary for River Rch & Prof#=Stream0039,Reach-1,6
Up Type=0
Dn Type=3
Dn Slope=0.005
Boundary for River Rch & Prof#=Stream0039,Reach-1,7
Up Type=0
Dn Type=3
Dn Slope=0.005

--- Stream0039.g01 (geometry) ---

Geom Title=Existing Conditions
Program Version=4.10

River Reach=Stream0039      ,Reach-1
Reach XY= 30
        1975525.       13922925.      1975482.95     13922881.11
      1975469.41     13922822.35      1975435.11     13922785.37
      1975414.66      13922776.1      1975322.33     13922769.58
      1975283.03     13922731.35      1975269.25     13922672.46
      1975238.62     13922638.28      1975214.54     13922626.15
      1975136.21     13922623.26      1975125.12     13922609.24
      1975128.13     13922577.17       1975168.8     13922527.23
      1975183.16     13922468.95      1975271.37      13922373.5
      1975280.54     13922272.58      1975366.84     13922181.05
      1975379.22     13922126.75       1975419.3     13922077.35
      1975425.24     13922050.08      1975425.32     13921949.89
      1975419.55     13921922.55      1975185.52     13921684.79
      1975176.17     13921664.52      1975174.86     13921595.06
      1975169.45     13921572.57      1975082.53     13921478.33
      1975090.99     13921458.33        1975175.       13921375.

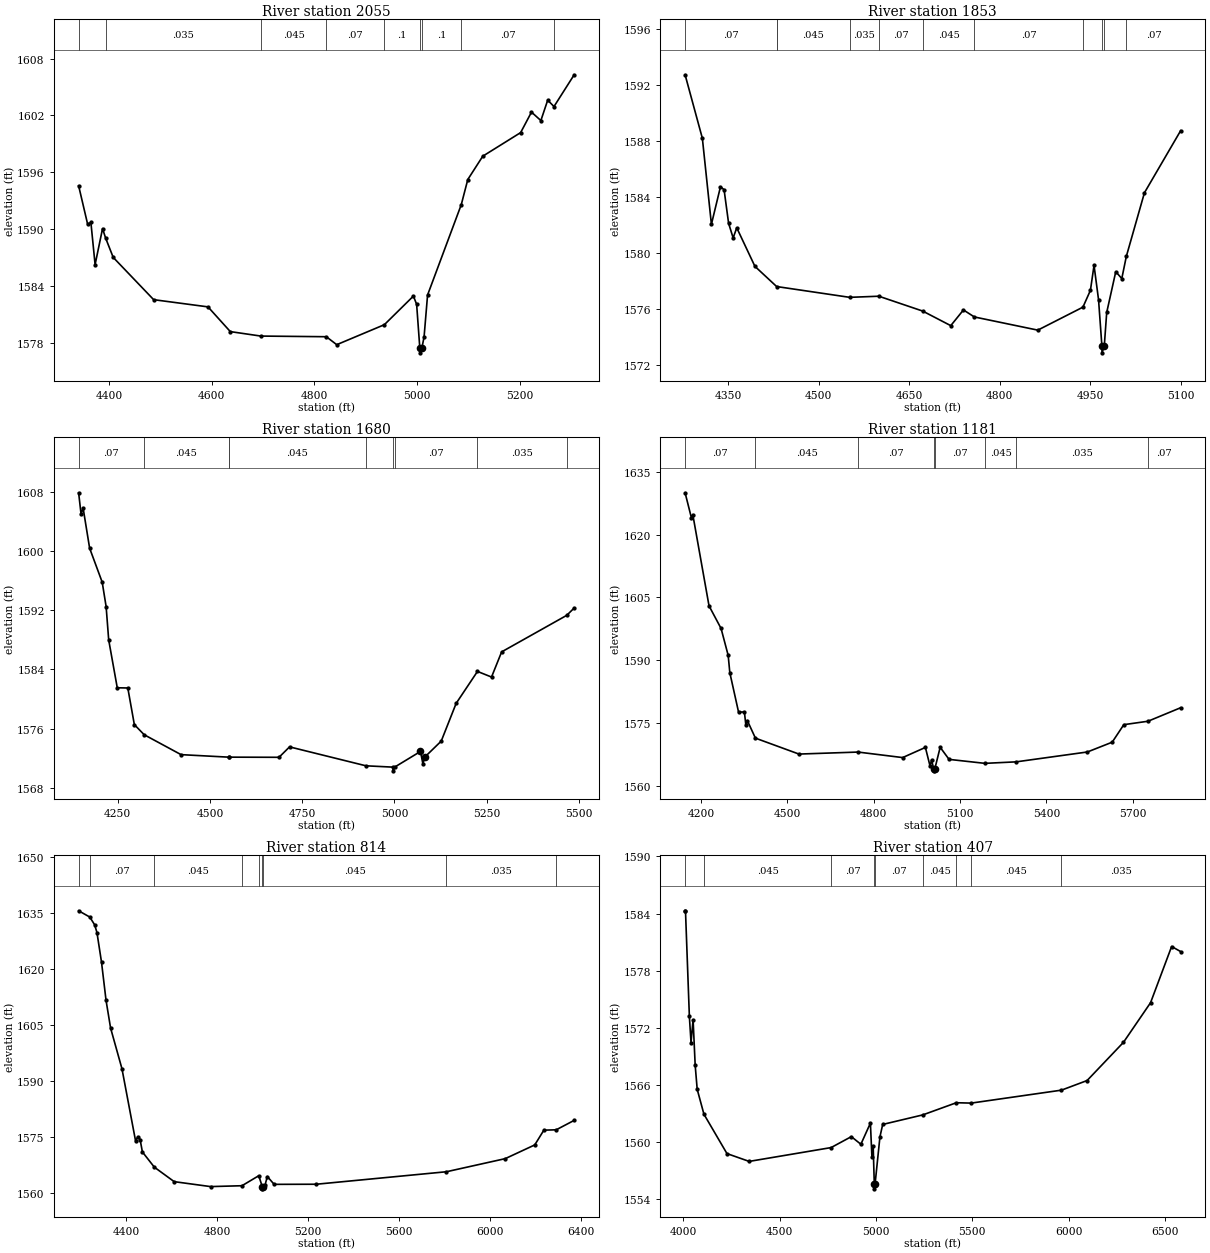
Type RM Length L Ch R = 1 ,2055    ,202,202,202
BEGIN DESCRIPTION:
Stream0039 6.0
END DESCRIPTION:
XS GIS Cut Line= 3
      1976022.99     13922498.52      1975411.01     13922971.62
      1975350.24     13923153.92
#Sta/Elev= 30
  4340.4 1594.58    4358 1590.51  4364.3 1590.71  4372.5 1586.26    4387 1590.06
    4393 1589.06  4407.8 1587.02  4486.6 1582.56  4592.5  1581.8    4636 1579.19
  4695.4 1578.72  4823.1 1578.65  4843.4 1577.81  4936.2 1579.92  4992.8 1582.94
  4999.1 1582.07  5005.3 1577.45  5005.6 1576.95  5009.3 1577.45  5013.6 1578.63
  5020.4 1583.05  5086.1 1592.59  5098.8 1595.24    5128  1597.7  5201.8 1600.19
  5222.9 1602.35  5241.2 1601.46  5254.5 1603.61  5266.8 1602.94  5306.1 1606.29
#Mann= 9 ,-1 , 0
  4340.4     .07       0    4393    .035       0  4695.4    .045       0
  4823.1     .07       0  4936.2      .1       0  5005.3     .05       0
  5009.3      .1       0  5086.1     .07       0  5266.8      .1       0
#Block Obstruct= 2 , 0
          4979.4 1581.34
Bank Sta=5005.3,5009.3
XS Rating Curve= 0 ,0
Exp/Cntr=0.3,0.1

Type RM Length L Ch R = 1 ,1853    ,173,173,173
BEGIN DESCRIPTION:
Stream0039 1.0
END DESCRIPTION:
XS GIS Cut Line= 3
      1975975.01     13922374.99        1975375.       13922775.
        1975375.     13922874.97
#Sta/Elev= 30
  4278.9 1592.73  4307.5  1588.2  4322.5 1582.06  4337.5 1584.74  4343.5 1584.53
    4351 1582.13  4358.5 1581.09  4364.5 1581.81  4394.6 1579.06  4430.6 1577.62
  4551.6 1576.85  4599.9 1576.93  4672.6 1575.87  4719.1 1574.83  4740.1 1575.95
  4758.2 1575.45  4863.3 1574.51  4938.1 1576.15  4950.5 1577.35  4956.5 1579.13
    4964 1576.67  4969.5 1573.39  4969.7 1572.89  4973.5 1573.39  4977.5 1575.77
  4992.5 1578.68  5002.5 1578.19    5010 1579.77    5040 1584.31    5100 1588.74
#Mann= 11 ,-1 , 0
  4278.9     .07       0  4430.6    .035       0  4430.6    .045       0
  4551.6    .035       0  4599.9     .07       0  4672.6    .045       0
  4758.2     .07       0  4938.1      .1       0  4969.5     .05       0
  4973.5      .1       0    5010     .07       0
#Block Obstruct= 2 , 0
         4955.88 1577.41
Bank Sta=4969.5,4973.5
XS Rating Curve= 0 ,0
Exp/Cntr=0.3,0.1

Type RM Length L Ch R = 1 ,1680    ,499,499,499
BEGIN DESCRIPTION:
Stream0039 5.0
END DESCRIPTION:
XS GIS Cut Line= 4
      1976022.95     13922285.87      1975319.86     13922602.69
      1975163.61     13922802.35      1975102.84     13923114.89
#Sta/Elev= 30
  4143.9 1607.89  4150.5    1605    4156 1605.84  4173.7  1600.4  4207.8  1595.8
  4218.4 1592.51  4225.4 1587.99  4248.6 1581.53  4277.2  1581.5  4294.9 1576.55
  4321.6 1575.18  4421.5 1572.49  4550.5 1572.15  4550.9 1572.15    4687 1572.13
  4715.6 1573.54  4922.7 1570.98  4996.3  1570.8  4996.5  1570.3  5000.3  1570.8
  5070.4 1572.92  5076.9 1571.28  5083.3 1572.22  5126.7 1574.32  5167.1 1579.42
  5224.9 1583.74    5263 1582.98  5290.4 1586.38  5466.8 1591.32    5487 1592.31
#Mann= 9 ,-1 , 0
  4143.9     .07       0  4321.6    .045       0  4550.5    .035       0
  4550.9    .045       0  4922.7     .07       0  4996.3     .05       0
  5000.3     .07       0  5224.9    .035       0  5466.8     .07       0
#Block Obstruct= 2 , 0
         5058.86 1573.06
Bank Sta=5070.4,5083.3
XS Rating Curve= 0 ,0
Exp/Cntr=0.3,0.1

Type RM Length L Ch R = 1 ,1181    ,367,367,367
BEGIN DESCRIPTION:
Stream0039 4.0
END DESCRIPTION:
XS GIS Cut Line= 4
      1976118.49     13922186.03      1975371.94     13922307.56
      1975046.42     13922385.68      1974950.99      13923010.3
#Sta/Elev= 30
    4144 1630.02  4165.7  1624.1  4170.8  1624.8  4227.2 1602.98  4269.1 1597.57
  4293.8 1591.14  4299.5    1587  4329.9 1577.57  4350.2 1577.61  4355.3 1574.43
  4360.4 1575.55  4388.5 1571.35  4539.9 1567.54  4745.5 1568.02  4900.4  1566.7
  4979.5 1569.13  4995.7 1564.67  5000.9  1566.1  5008.4 1564.03  5008.6 1563.53
  5012.4 1564.03  5030.9 1569.16  5061.8 1566.27  5186.4 1565.32  5295.3 1565.68
  5542.8 1568.04    5629 1570.38  5669.4 1574.57  5753.5 1575.39    5867 1578.62
#Mann= 8 ,-1 , 0
    4144     .07       0  4388.5    .045       0  4745.5     .07       0
  5008.4     .05       0  5012.4     .07       0  5186.4    .045       0
  5295.3    .035       0  5753.5     .07       0
#Block Obstruct= 2 , 0
                         5030.74          1567.9
Bank Sta=5008.4,5012.4
XS Rating Curve= 0 ,0
Exp/Cntr=0.3,0.1

Type RM Length L Ch R = 1 ,814     ,407,407,407
BEGIN DESCRIPTION:
Stream0039 3.0
END DESCRIPTION:
XS GIS Cut Line= 4
      1976235.66     13922016.76      1975220.03     13922016.76
      1974920.55     13922316.24      1974916.21     13923058.47
#Sta/Elev= 30
  4189.8  1635.5    4239 1633.82  4260.5 1631.72  4270.5 1629.67  4290.5 1621.77
  4310.5 1611.55  4330.5 1604.15  4380.5 1593.29  4440.5 1573.97  4450.5 1575.13
  4460.5 1574.33  4470.5 1571.04  4523.1 1566.97  4610.5  1563.1  4770.5 1561.78
  4908.8 1562.01  4982.9 1564.69  4998.5 1561.68  4998.7 1561.18  5002.5 1561.68
  5010.5 1562.23  5020.5 1564.47  5050.5 1562.38    5236 1562.41  5808.9 1565.75
  6067.7 1569.25  6197.7 1572.92  6237.7 1576.86  6292.2 1576.96  6371.2 1579.48
#Mann= 9 ,-1 , 0
  4189.8      .1       0    4239     .07       0  4523.1    .045       0
  4908.8     .07       0  4982.9    .045       0  4998.5    .045       0
  5002.5    .045       0  5808.9    .035       0  6292.2     .07       0
#Block Obstruct= 2 , 0
                         5030.61         1564.02
Bank Sta=4998.5,5002.5
XS Rating Curve= 0 ,0
Exp/Cntr=0.3,0.1

Type RM Length L Ch R = 1 ,407     ,0,0,0
BEGIN DESCRIPTION:
Stream0039 2.0
END DESCRIPTION:
XS GIS Cut Line= 4
      1976083.78     13921786.74      1975406.67     13921530.65
      1974859.79     13921982.04      1974825.12     13923121.78
#Sta/Elev= 30
  4008.5 1584.29  4010.5 1584.29  4030.7  1573.2  4039.3 1570.46    4050 1572.86
  4060.9 1568.06  4071.3 1565.55  4106.4 1562.93  4225.9  1558.8  4341.2 1557.98
  4766.6 1559.43  4871.8 1560.58  4921.3 1559.78  4970.8    1562  4978.6 1558.48
  4985.1 1559.63    4991  1555.6  4991.2  1555.1    4995  1555.6  5020.3 1560.56
  5034.6 1561.86  5242.5 1562.86  5417.2 1564.14    5494  1564.1    5963 1565.46
  6096.1 1566.47  6284.9 1570.48  6425.6 1574.64    6535 1580.54  6581.8 1580.01
#Mann= 9 ,-1 , 0
  4008.5     .07       0  4106.4    .045       0  4766.6     .07       0
    4991     .05       0    4995     .07       0  5242.5    .045       0
  5417.2     .07       0    5494    .045       0    5963    .035       0
Bank Sta=4991,4995
XS Rating Curve= 0 ,0
Exp/Cntr=0.3,0.1

Chan Stop Cuts=-1
Use User Specified Reach Order=0
Composite Channel Slope=5