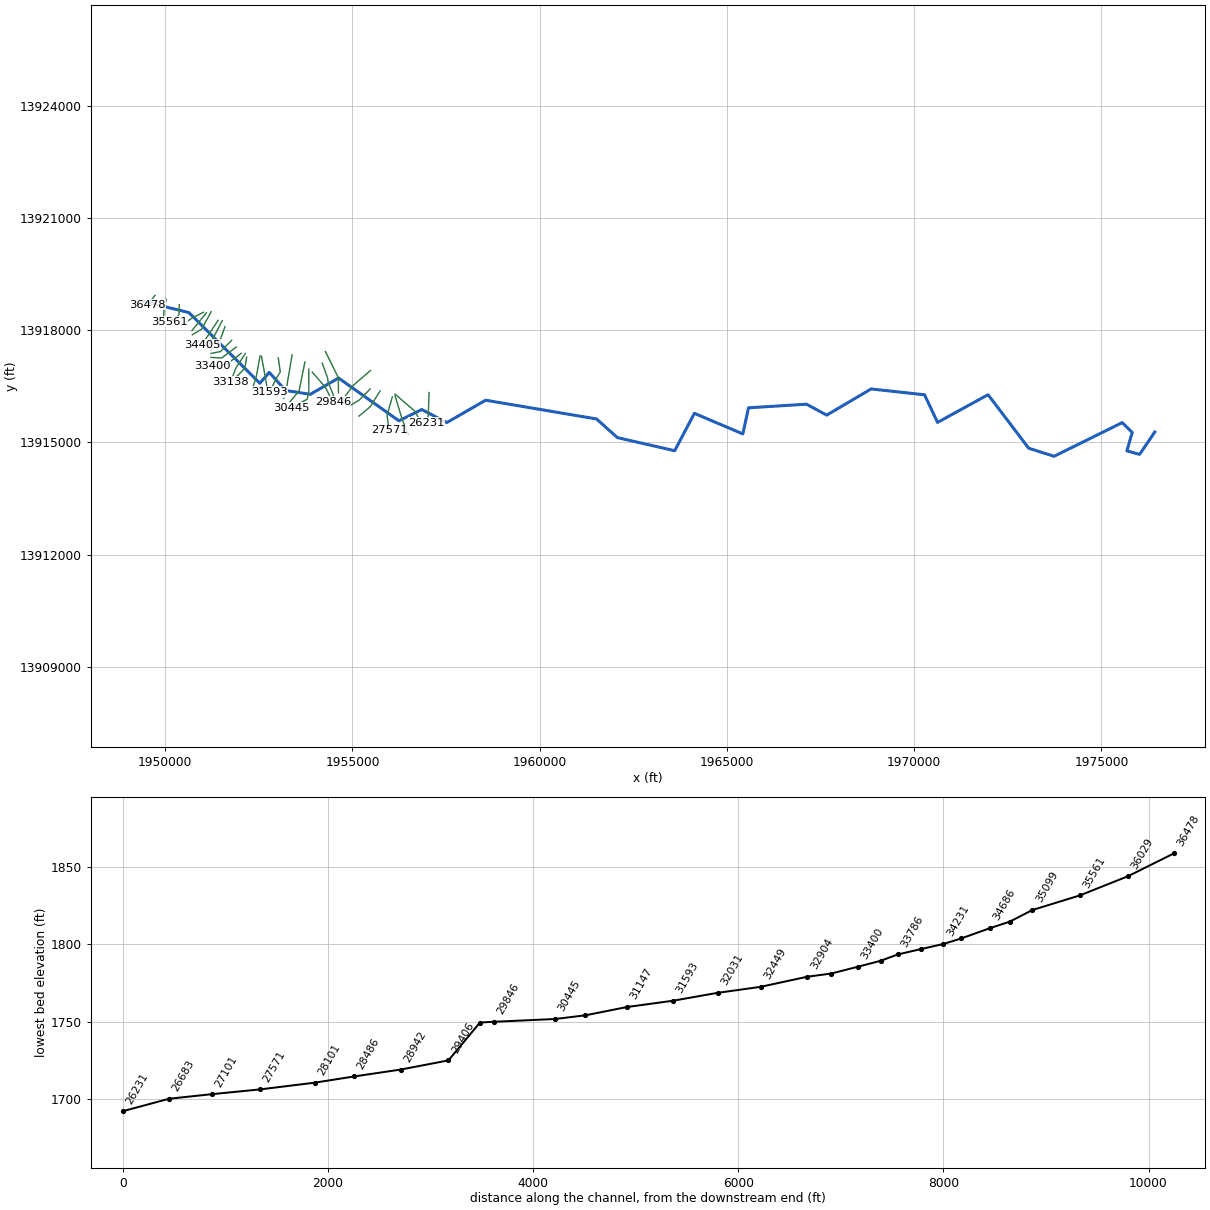
--- Stream0040.prj (project) ---

Proj Title=Stream0040 Base Level Engineering
Current Plan=p01
Default Exp/Contr=0.3,0.1
English Units
Geom File=g01
Flow File=f01
Plan File=p01
Y Axis Title=Elevation
X Axis Title(PF)=Main Channel Distance
X Axis Title(XS)=Station
BEGIN DESCRIPTION:
Stream0040
END DESCRIPTION:
DSS Export Rating Curves= 0
DSS Export Rating Curve Sorted= 0
DSS Export Volume Flow Curves= 0
DXF OffsetX= 0
DXF OffsetY= 0
DXF ScaleX= 1
DXF ScaleY= 10

--- Stream0040.p01 (plan) ---

Plan Title=Multiple Run
Short Identifier=Multiple
Geom File=g01
Flow File=f01
Subcritical Flow
K Sum by GR= 0
Std Step Tol= 0.01
Critical Tol= 0.01
Num of Std Step Trials= 20
Max Error Tol= 0.3
Flow Tol Ratio= 0.001
Split Flow NTrial= 30
Split Flow Tol= 0.02
Split Flow Ratio= 0.02
Log Output Level= 0
Friction Slope Method= 1
Unsteady Friction Slope Method= 2
Unsteady Bridges Friction Slope Method= 1
Parabolic Critical Depth
Global Vel Dist=  1 , 1 , 1
Global Log Level= 0
CheckData=True
Encroach Param= -1, 0, 0, 0
BEGIN DESCRIPTION:
Multiple Run
END DESCRIPTION:

--- Stream0040.f01 (steady flow) ---

Flow Title=Multiple
Number of Profiles=7
Profile Names=10-year,25-year,50-year,1pct_min,100-year,1pct_plu,500-year
River Rch & RM= Stream0040,Reach-1,36478
     452     726     974     636    1268    2531    2112
River Rch & RM= Stream0040,Reach-1,35561
     866    1452    2003    1340    2673    5334    4689
River Rch & RM= Stream0040,Reach-1,33138
    1786    3124    4432    3037    6060   12091   11186
River Rch & RM= Stream0040,Reach-1,29846
    2799    5016    7231    5027   10030   20012   19066
River Rch & RM= Stream0040,Reach-1,27571
    2838    5081    7319    5083   10142   20235   19242
River Rch & RM= Stream0040,Reach-1,26231
    2982    5342    7698    5346   10668   21285   20244
River Rch & RM= Stream0040,Reach-1,24320
    3587    6479    9385    6548   13065   26068   25024
River Rch & RM= Stream0040,Reach-1,22007
    4282    7791   11340    7946   15854   31633   30629
River Rch & RM= Stream0040,Reach-1,20195
    4391    7982   11610    8127   16216   32356   31271
River Rch & RM= Stream0040,Reach-1,17373
    5310    9723   14214    9993   19939   39783   38785
River Rch & RM= Stream0040,Reach-1,15773
    5643   10340   15121   10631   21213   42325   41269
River Rch & RM= Stream0040,Reach-1,11910
    5732   10498   15346   10784   21517   42931   41818
River Rch & RM= Stream0040,Reach-1,9839
    3770    6816    9889    6924   13815   27565   26786
River Rch & RM= Stream0040,Reach-1,6479
    3823    6899    9997    6990   13946   27826   26960
Boundary for River Rch & Prof#=Stream0040,Reach-1,1
Up Type=0
Dn Type=3
Dn Slope=0.005
Boundary for River Rch & Prof#=Stream0040,Reach-1,2
Up Type=0
Dn Type=3
Dn Slope=0.005
Boundary for River Rch & Prof#=Stream0040,Reach-1,3
Up Type=0
Dn Type=3
Dn Slope=0.005
Boundary for River Rch & Prof#=Stream0040,Reach-1,4
Up Type=0
Dn Type=3
Dn Slope=0.005
Boundary for River Rch & Prof#=Stream0040,Reach-1,5
Up Type=0
Dn Type=3
Dn Slope=0.005
Boundary for River Rch & Prof#=Stream0040,Reach-1,6
Up Type=0
Dn Type=3
Dn Slope=0.005
Boundary for River Rch & Prof#=Stream0040,Reach-1,7
Up Type=0
Dn Type=3
Dn Slope=0.005

--- Stream0040.g01 (geometry) ---

Geom Title=Existing Conditions
Program Version=4.10

River Reach=Stream0040      ,Reach-1
Reach XY= 30
        1949375.       13918775.      1950631.33       13918467.
      1952526.64     13916578.09      1952778.22     13916867.17
      1953218.31     13916384.28      1953875.01     13916282.22
      1954628.31     13916716.98      1956240.39     13915575.07
      1956850.36     13915875.64      1957519.11     13915526.96
       1958556.8     13916124.88      1961519.15     13915622.94
        1962075.       13915125.      1963604.96     13914775.05
      1964130.97     13915772.83        1965425.       13915225.
      1965576.25     13915921.55      1967125.01     13916018.41
       1967664.5      13915726.2      1968849.99     13916425.59
      1970277.31     13916269.18       1970625.1     13915532.31
      1971973.26     13916271.69      1973058.32     13914841.64
       1973735.5     13914626.19      1975554.86      13915525.4
      1975823.78      13915264.5      1975680.29     13914772.33
      1976019.33     13914676.98        1976425.       13915275.

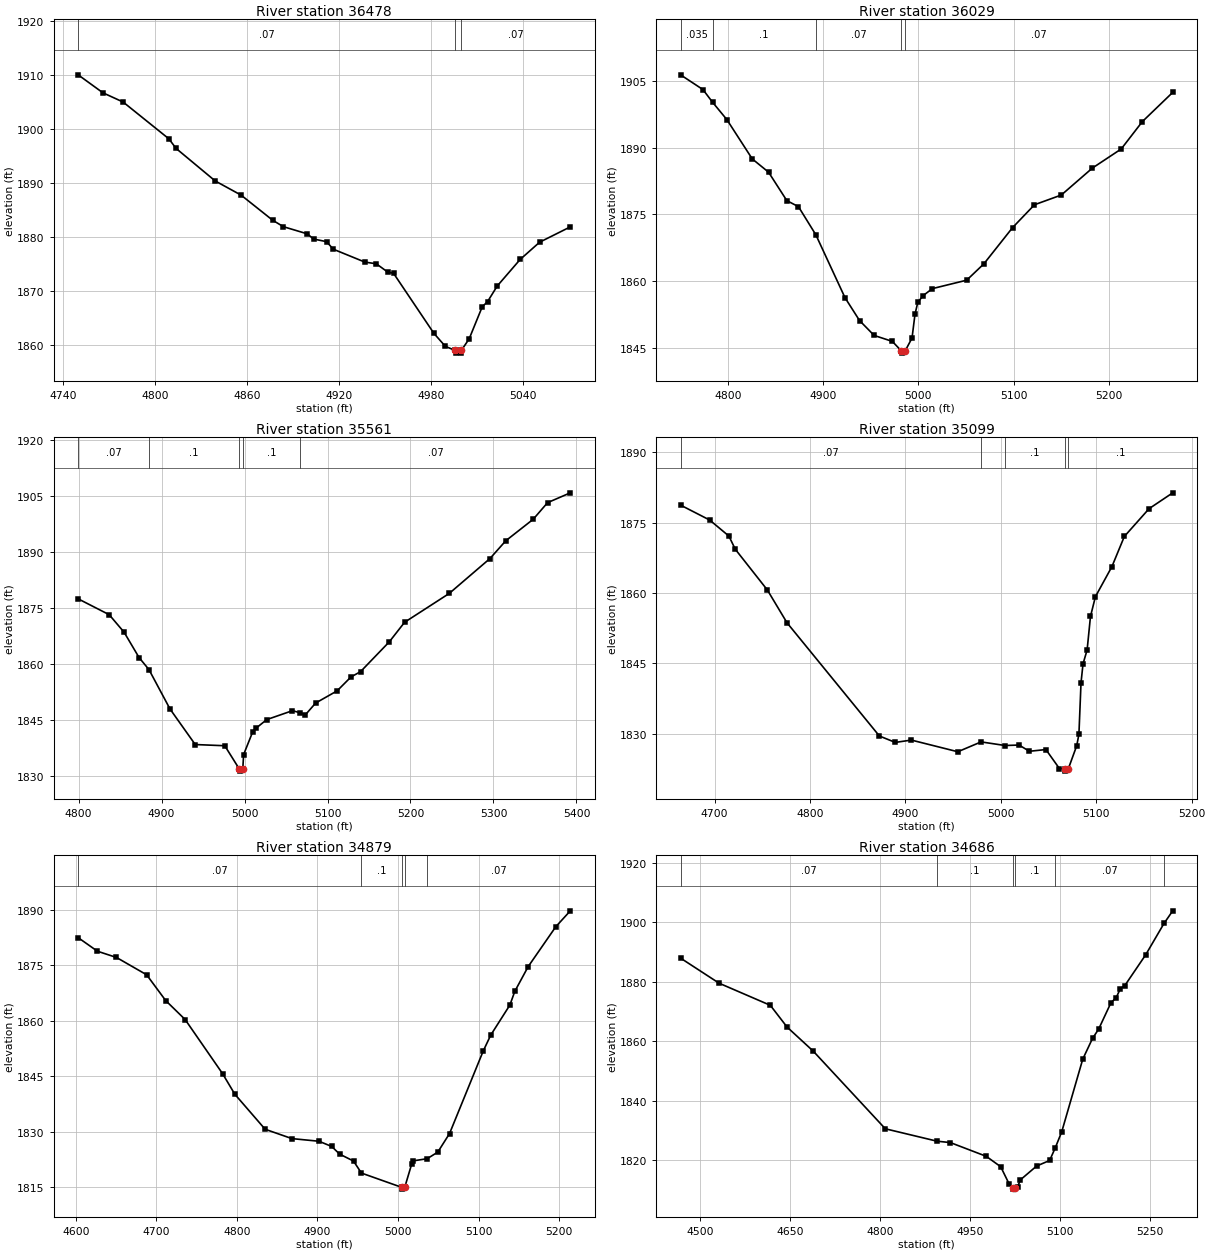
Type RM Length L Ch R = 1 ,36478   ,449,449,449
BEGIN DESCRIPTION:
Stream0040 64.0
END DESCRIPTION:
XS GIS Cut Line= 3
        1949725.       13918925.        1949575.       13918725.
      1949525.01     13918675.01
#Sta/Elev= 30
    4750 1910.05  4766.2 1906.71  4779.3 1905.01  4809.1  1898.2  4813.8 1896.42
  4839.3 1890.39  4856.2 1887.76  4876.8  1883.1  4883.8 1881.91  4899.3 1880.59
  4903.4 1879.63  4911.9 1879.14  4916.2 1877.75  4936.8 1875.36  4944.3 1875.04
  4951.8 1873.49  4955.5 1873.29  4981.8 1862.16  4989.3 1859.74  4995.7 1858.99
  4995.9 1858.49  4999.4 1858.49  4999.7 1858.99  5004.8 1861.14  5013.3 1867.07
  5016.8 1868.04  5023.1 1870.93    5038 1875.84  5050.7 1879.04  5070.7 1881.88
#Mann= 3 ,-1 , 0
    4750     .07       0  4995.7     .05       0  4999.7     .07       0
Bank Sta=4995.7,4999.7
XS Rating Curve= 0 ,0
Exp/Cntr=0.3,0.1

Type RM Length L Ch R = 1 ,36029   ,468,468,468
BEGIN DESCRIPTION:
Stream0040 63.0
END DESCRIPTION:
XS GIS Cut Line= 3
        1950025.     13918824.98        1949975.       13918575.
      1949951.54     13918314.08
#Sta/Elev= 30
  4750.2 1906.36  4773.7 1903.04  4783.8 1900.19  4798.8 1896.29  4825.5 1887.44
  4842.6 1884.46  4861.8 1878.06    4874  1876.7  4892.3 1870.36  4922.9 1856.22
  4938.2 1851.07  4953.5 1847.73  4972.6 1846.39  4982.1 1844.25  4982.4 1843.75
  4986.1 1844.25  4993.3 1847.16  4996.4  1852.5  4999.4 1855.21  5005.1 1856.71
  5014.6 1858.26  5050.7 1860.16  5068.8 1863.85  5098.9 1871.99  5121.9 1877.13
  5150.1 1879.32  5182.7 1885.38    5213 1889.68  5235.2 1895.84  5267.1 1902.41
#Mann= 5 ,-1 , 0
  4750.2    .035       0  4783.8      .1       0  4892.3     .07       0
  4982.1     .05       0  4986.1     .07       0
Bank Sta=4982.1,4986.1
XS Rating Curve= 0 ,0
Exp/Cntr=0.3,0.1

Type RM Length L Ch R = 1 ,35561   ,462,462,462
BEGIN DESCRIPTION:
Stream0040 62.0
END DESCRIPTION:
XS GIS Cut Line= 4
        1950375.       13918675.        1950375.       13918475.
      1950350.01      13918378.4      1950104.61     13918217.73
#Sta/Elev= 30
  4799.5  1877.5  4836.9 1873.26  4854.9 1868.56  4872.9  1861.8  4884.9 1858.55
  4910.2 1848.04  4940.6 1838.53  4976.2 1838.21  4993.9 1831.92  4994.2 1831.42
  4997.9 1831.92  4998.9 1835.84  5009.9 1841.95  5014.4    1843  5026.8  1845.2
  5057.8 1847.59  5067.3 1847.01  5073.3 1846.47  5085.7 1849.63  5111.6 1852.89
  5128.3 1856.61  5139.8 1858.02  5174.5 1866.01  5192.9 1871.23  5246.7 1878.94
  5295.8 1888.28  5314.8 1893.02  5347.9 1898.78  5365.2 1903.22  5392.6 1905.85
#Mann= 5 ,-1 , 0
  4799.5     .07       0  4884.9      .1       0  4993.9     .05       0
  4997.9      .1       0  5067.3     .07       0
Bank Sta=4993.9,4997.9
XS Rating Curve= 0 ,0
Exp/Cntr=0.3,0.1

Type RM Length L Ch R = 1 ,35099   ,220,220,220
BEGIN DESCRIPTION:
Stream0040 61.0
END DESCRIPTION:
XS GIS Cut Line= 3
      1951024.98     13918474.99        1950725.       13918325.
      1950574.97     13918224.98
#Sta/Elev= 30
  4664.4 1878.73  4694.9 1875.55    4715 1872.14  4721.7 1869.33  4755.3 1860.65
    4776 1853.63  4872.7 1829.52  4889.4 1828.15  4906.2 1828.65  4954.9 1826.16
  4979.3 1828.26  5004.4 1827.49  5019.1 1827.59  5029.9 1826.26  5047.2 1826.63
  5061.4 1822.57  5066.7 1822.53  5066.9 1822.03  5070.7 1822.53  5079.5 1827.45
  5081.8 1829.89    5084 1840.86  5086.1  1844.9  5090.4 1847.86  5093.9 1854.99
  5099.1 1859.22  5116.4 1865.63  5129.4 1872.05  5155.3 1877.97  5180.1 1881.35
#Mann= 5 ,-1 , 0
  4664.4     .07       0  4979.3    .035       0  5004.4      .1       0
  5066.7     .05       0  5070.7      .1       0
Bank Sta=5066.7,5070.7
XS Rating Curve= 0 ,0
Exp/Cntr=0.3,0.1

Type RM Length L Ch R = 1 ,34879   ,193,193,193
BEGIN DESCRIPTION:
Mapping XS 0bae6a1b
END DESCRIPTION:
XS GIS Cut Line= 2
      1951099.39     13918458.52      1950713.31     13917985.08
#Sta/Elev= 30
  4602.9 1882.44  4626.8 1878.78  4650.5 1877.09  4687.9 1872.42  4711.6 1865.45
  4735.7 1860.34  4782.2 1845.72  4797.4 1840.17    4835 1830.72  4868.2  1828.2
  4901.9 1827.48  4917.7 1826.07  4927.4 1824.02  4944.7 1822.14  4954.5  1818.9
  5004.3 1815.06  5004.6 1814.56  5008.3 1815.06    5017  1821.4  5019.1  1822.2
  5036.1 1822.77  5049.3 1824.55  5063.9 1829.56  5105.6 1851.79    5115 1856.12
  5138.8 1864.25  5144.9 1867.94  5161.5 1874.62  5195.8 1885.39  5213.8 1889.68
#Mann= 5 ,-1 , 0
  4602.9     .07       0  4954.5      .1       0  5004.3     .05       0
  5008.3      .1       0  5036.1     .07       0
Bank Sta=5004.3,5008.3
XS Rating Curve= 0 ,0
Exp/Cntr=0.3,0.1

Type RM Length L Ch R = 1 ,34686   ,281,281,281
BEGIN DESCRIPTION:
Stream0040 60.0
END DESCRIPTION:
XS GIS Cut Line= 3
      1951226.79     13918490.11        1950975.       13918025.
      1950725.03     13917875.02
#Sta/Elev= 30
  4466.9 1887.92  4531.2 1879.49  4616.5 1872.08  4644.4 1864.78  4688.1 1856.68
  4808.2 1830.62  4894.5 1826.45  4916.6 1825.99  4976.4 1821.38  5000.5 1817.89
  5014.8 1812.01  5020.5 1810.86  5020.8 1810.36  5024.5 1810.86  5028.8  1811.2
  5033.5  1813.5  5060.3  1818.1  5082.1 1819.98  5091.4 1824.18  5102.3 1829.63
  5137.3 1853.99  5153.7 1861.01  5163.7 1864.04  5184.4 1872.98  5192.9 1874.61
  5200.2 1877.72  5207.2 1878.64  5242.2 1889.03  5272.7 1899.55  5287.3  1903.8
#Mann= 6 ,-1 , 0
  4466.9     .07       0  4894.5      .1       0  5020.5     .05       0
  5024.5      .1       0  5091.4     .07       0  5272.7    .035       0
Bank Sta=5020.5,5024.5
XS Rating Curve= 0 ,0
Exp/Cntr=0.3,0.1

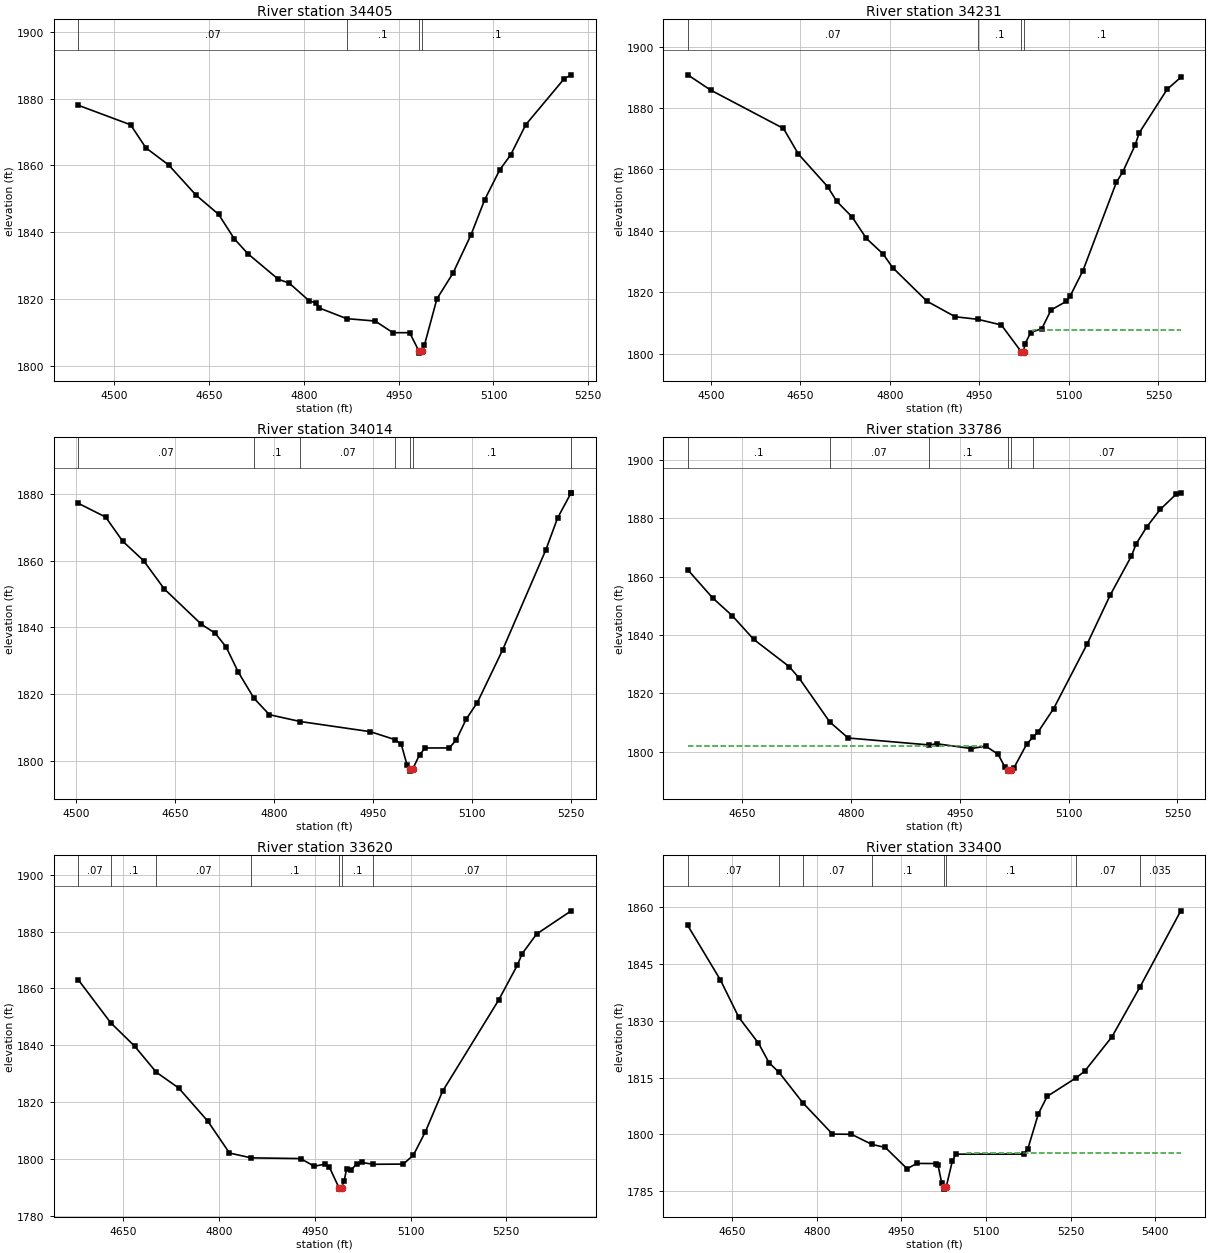
Type RM Length L Ch R = 1 ,34405   ,174,174,174
BEGIN DESCRIPTION:
Mapping XS 7cbe28e7
END DESCRIPTION:
XS GIS Cut Line= 2
      1951412.46     13918258.92      1950982.12     13917608.37
#Sta/Elev= 30
    4443 1878.03  4525.9 1872.17  4550.1 1865.25  4586.1 1860.13  4629.2 1851.12
  4665.2  1845.3  4689.9    1838  4711.5  1833.5  4759.8 1825.82  4776.7 1824.72
  4808.9 1819.32  4819.8 1818.76  4824.1 1817.27  4867.7 1814.05  4912.8 1813.33
    4941 1809.83  4967.4 1809.84  4982.3 1804.21  4982.5 1803.71  4986.3 1804.21
  4990.8 1806.15  5010.5 1819.99  5035.7 1827.61  5064.5 1839.21  5086.1 1849.71
  5109.8 1858.63  5127.2 1863.15    5151 1872.18  5211.9 1885.99    5223 1887.15
#Mann= 4 ,-1 , 0
    4443     .07       0  4867.7      .1       0  4982.3     .05       0
  4986.3      .1       0
Bank Sta=4982.3,4986.3
XS Rating Curve= 0 ,0
Exp/Cntr=0.3,0.1

Type RM Length L Ch R = 1 ,34231   ,217,217,217
BEGIN DESCRIPTION:
Stream0040 59.0
END DESCRIPTION:
XS GIS Cut Line= 3
      1951522.72     13918248.82        1951275.       13917775.
      1951125.01     13917525.02
#Sta/Elev= 30
  4461.2  1890.8  4499.8 1885.81  4621.7 1873.33  4646.6 1865.01  4695.5 1854.41
  4711.1 1849.55  4736.8 1844.47  4760.5 1837.53  4788.9 1832.38  4804.4 1828.04
  4862.1 1817.06  4909.4    1812  4947.4 1811.16  4986.8 1809.31  5019.9 1800.65
  5020.1 1800.15  5023.9 1800.65  5026.3 1803.13    5036 1806.85  5054.7 1808.17
    5070 1814.21  5095.5    1817  5102.5 1818.91  5123.5 1827.02  5179.4 1855.73
  5190.3 1859.22  5210.9 1867.91  5217.9 1871.94  5264.6 1886.08  5287.4 1889.97
#Mann= 4 ,-1 , 0
  4461.2     .07       0  4947.4      .1       0  5019.9     .05       0
  5023.9      .1       0
#XS Ineff= 2 , 0
                         5039.35          1807.8
Permanent Ineff=
       F       F
Bank Sta=5019.9,5023.9
XS Rating Curve= 0 ,0
Exp/Cntr=0.3,0.1

Type RM Length L Ch R = 1 ,34014   ,228,228,228
BEGIN DESCRIPTION:
Mapping XS 6030e070
END DESCRIPTION:
XS GIS Cut Line= 3
      1951596.88     13918091.71      1951434.33      13917644.5
      1951222.75     13917474.43
#Sta/Elev= 30
  4503.6 1877.31  4545.2 1873.16    4571 1865.92  4602.7 1860.07  4634.2 1851.55
  4690.3 1840.96  4711.2  1838.3  4727.8 1834.14  4746.5 1826.51  4770.1 1818.73
  4793.4 1813.82    4840 1811.77  4946.5 1808.71  4983.3 1806.36  4993.3 1804.89
  5001.9 1798.81  5006.3 1797.37  5006.5 1796.87  5010.3 1797.37  5021.1 1801.83
  5029.6 1803.82  5065.9 1803.83  5076.6  1806.2  5091.5 1812.42  5108.6 1817.47
    5147 1833.32  5212.5 1863.36  5230.2 1872.88  5250.4 1880.33  5250.9 1880.44
#Mann= 7 ,-1 , 0
  4503.6     .07       0  4770.1      .1       0    4840     .07       0
  4983.3      .1       0  5006.3     .05       0  5010.3      .1       0
  5250.4     .07       0
Bank Sta=5006.3,5010.3
XS Rating Curve= 0 ,0
Exp/Cntr=0.3,0.1

Type RM Length L Ch R = 1 ,33786   ,166,166,166
BEGIN DESCRIPTION:
Stream0040 58.0
END DESCRIPTION:
XS GIS Cut Line= 3
        1951775.       13917725.        1951475.       13917425.
      1951225.01       13917375.
#Sta/Elev= 30
  4575.3 1862.39  4609.7 1852.72  4636.6 1846.65  4666.3 1838.51  4715.1  1829.2
  4728.5 1825.35  4770.9 1810.26  4796.3 1804.74  4907.1 1802.38  4918.7 1802.75
    4966 1801.13    4986 1801.94  5002.9 1799.15  5012.1 1794.85  5016.2 1793.89
  5016.5 1793.39  5020.2 1793.89  5024.8 1794.57  5042.4  1802.7  5051.4 1805.17
    5058 1806.82  5079.4 1814.82  5125.3 1836.83  5157.4 1853.75  5186.5 1867.07
  5193.1 1871.28  5207.9 1877.15  5226.3 1883.08  5247.7 1888.17  5254.5 1888.74
#Mann= 6 ,-1 , 0
  4575.3      .1       0  4770.9     .07       0  4907.1      .1       0
  5016.2     .05       0  5020.2      .1       0  5051.4     .07       0
#XS Ineff= 2 , 0
         4980.83 1801.86
Permanent Ineff=
       F       F
Bank Sta=5016.2,5020.2
XS Rating Curve= 0 ,0
Exp/Cntr=0.3,0.1

Type RM Length L Ch R = 1 ,33620   ,220,220,220
BEGIN DESCRIPTION:
Mapping XS 055e5812
END DESCRIPTION:
XS GIS Cut Line= 3
      1951894.32     13917544.88       1951509.9     13917254.75
      1951219.44     13917268.52
#Sta/Elev= 30
  4579.4 1863.08  4630.3 1847.92  4667.9 1839.65  4701.7  1830.5  4736.8 1824.94
  4782.4 1813.28  4816.4 1802.04  4850.3 1800.34  4927.8 1800.09  4949.2 1797.38
  4966.3 1798.15  4972.7 1797.15  4987.9 1789.83  4988.1 1789.33  4991.9 1789.83
  4996.1 1792.29  4999.9 1796.48  5006.5 1795.93  5015.6 1798.22  5024.1 1798.71
  5041.3 1798.08  5088.7 1798.15  5104.5  1801.3  5123.3 1809.54  5150.3 1823.82
  5237.9 1855.83  5267.4 1868.19  5274.7 1872.14  5297.5 1879.15  5351.8 1887.32
#Mann= 7 ,-1 , 0
  4579.4     .07       0  4630.3      .1       0  4701.7     .07       0
  4850.3      .1       0  4987.9     .05       0  4991.9      .1       0
  5041.3     .07       0
#XS Ineff= 2 , 0
         4962.39 1797.77 5024.33         1798.51
Permanent Ineff=
       F       F
Bank Sta=4987.9,4991.9
XS Rating Curve= 0 ,0
Exp/Cntr=0.3,0.1

Type RM Length L Ch R = 1 ,33400   ,262,262,262
BEGIN DESCRIPTION:
Stream0040 57.0
END DESCRIPTION:
XS GIS Cut Line= 4
      1952025.03     13917375.02      1951670.45     13917108.83
        1951425.       13917025.      1951254.56      13917047.7
#Sta/Elev= 30
  4570.9 1855.24  4628.8 1840.86  4661.6 1830.93  4696.4 1824.12  4715.1 1818.97
  4733.1 1816.36  4774.7 1808.42  4827.7 1800.07  4861.4 1800.02  4897.5 1797.35
  4921.4 1796.55    4960 1790.93  4977.7 1792.32  5011.4 1792.28  5015.1 1791.77
  5021.4  1787.2  5025.4 1786.02  5025.7 1785.52  5029.4 1786.02  5040.4 1792.99
  5046.6 1794.76  5167.1 1794.78  5174.2 1796.13  5193.1 1805.47  5208.5 1810.03
  5259.5 1814.91    5275 1816.68  5323.4 1825.77    5373 1838.91  5445.6 1859.11
#Mann= 8 ,-1 , 0
  4570.9     .07       0  4733.1    .035       0  4774.7     .07       0
  4897.5      .1       0  5025.4     .05       0  5029.4      .1       0
  5259.5     .07       0    5373    .035       0
#XS Ineff= 2 , 0
                         5067.17            1795
Permanent Ineff=
       F       F
Bank Sta=5025.4,5029.4
XS Rating Curve= 0 ,0
Exp/Cntr=0.3,0.1

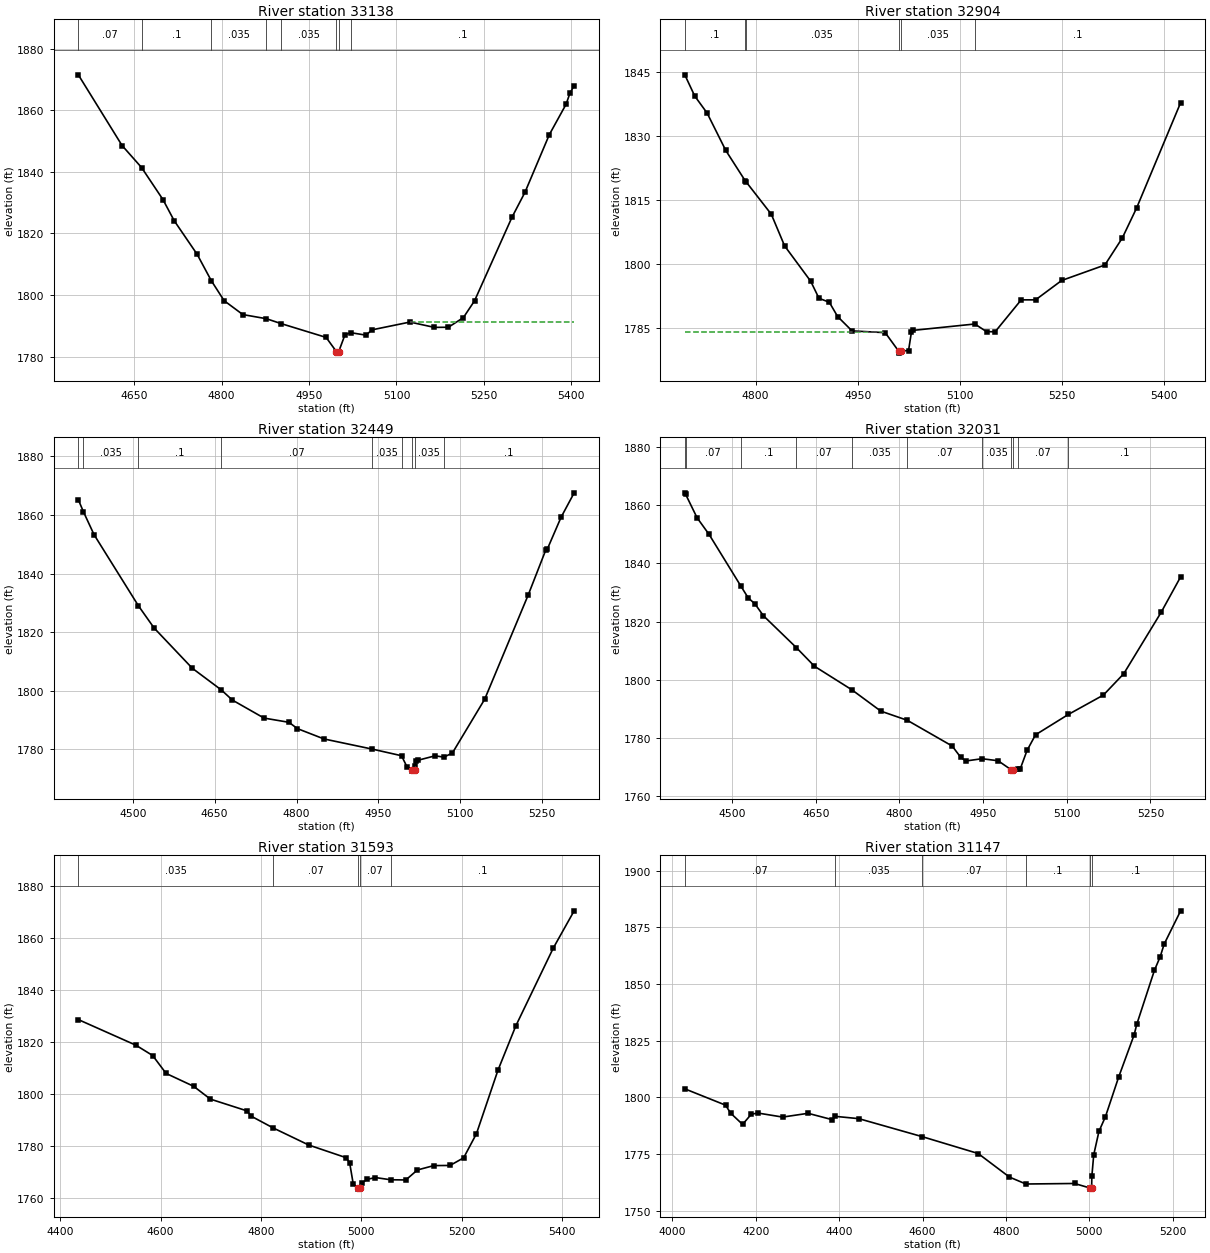
Type RM Length L Ch R = 1 ,33138   ,234,234,234
BEGIN DESCRIPTION:
Mapping XS c3aa3ae1
END DESCRIPTION:
XS GIS Cut Line= 3
      1952140.32     13917374.53      1951886.42     13916981.75
      1951751.88     13916623.69
#Sta/Elev= 30
  4554.5 1871.57  4629.5 1848.59  4662.9 1841.44  4699.6 1831.02  4718.8 1824.17
  4758.3  1813.2  4782.4 1804.68  4804.5 1798.15  4836.6 1793.63  4876.9 1792.29
    4902 1790.71  4979.4 1786.21    4997  1781.6  4997.2  1781.1    5001  1781.6
  5011.7 1787.06  5021.6 1787.75    5048 1786.93  5057.6 1788.65  5123.1  1791.2
    5165 1789.47    5189 1789.51  5214.7 1792.64  5233.9 1798.11    5298 1825.24
  5320.4  1833.4  5362.1 1852.12  5390.9 1862.02  5397.3 1865.53  5404.7 1868.09
#Mann= 8 ,-1 , 0
  4554.5     .07       0  4662.9      .1       0  4782.4    .035       0
  4876.9     .07       0    4902    .035       0    4997    .035       0
    5001    .035       0  5021.6      .1       0
#XS Ineff= 2 , 0
                         5123.31         1791.28
Permanent Ineff=
       F       F
Bank Sta=4997,5001
XS Rating Curve= 0 ,0
Exp/Cntr=0.3,0.1

Type RM Length L Ch R = 1 ,32904   ,455,455,455
BEGIN DESCRIPTION:
Stream0040 56.0
END DESCRIPTION:
XS GIS Cut Line= 3
        1952175.     13917274.99        1952125.       13916975.
      1951824.99     13916674.99
#Sta/Elev= 30
  4695.9  1844.3  4710.5 1839.33  4728.7 1835.33  4756.1 1826.57  4784.6 1819.47
    4786  1819.2    4823 1811.61  4842.5  1804.2  4880.8 1795.92    4893 1791.91
  4908.2 1790.98  4920.4 1787.63  4941.6 1784.26  4990.3 1783.85  5009.9 1779.55
  5010.2 1779.05  5013.9 1779.55  5024.6 1779.65  5028.9 1784.05  5030.9 1784.38
    5122 1785.88  5139.2 1784.08  5151.8 1784.06  5190.1 1791.54  5211.2 1791.54
  5249.5 1796.08    5313 1799.71  5338.6 1806.04  5359.7  1813.1  5424.3 1837.77
#Mann= 6 ,-1 , 0
  4695.9      .1       0  4784.6     .07       0    4786    .035       0
  5009.9    .035       0  5013.9    .035       0    5122      .1       0
#XS Ineff= 2 , 0
         4987.57 1784.09
Permanent Ineff=
       F       F
Bank Sta=5009.9,5013.9
XS Rating Curve= 0 ,0
Exp/Cntr=0.3,0.1

Type RM Length L Ch R = 1 ,32449   ,418,418,418
BEGIN DESCRIPTION:
Stream0040 55.0
END DESCRIPTION:
XS GIS Cut Line= 3
      1952532.87     13917306.95        1952425.       13916725.
        1952325.     13916424.99
#Sta/Elev= 30
  4400.4 1865.22  4409.8 1861.09  4429.2 1853.29  4510.4 1829.01  4539.1 1821.43
  4609.1 1807.67  4662.2 1800.27  4682.5  1796.8  4740.5 1790.65  4786.2  1789.2
  4801.5 1787.06  4850.3 1783.52  4938.7 1780.05  4992.3 1777.79  5002.3    1774
  5012.2 1773.03  5012.4 1772.53  5016.2 1773.03  5016.5 1774.32  5018.9 1775.92
  5022.2 1776.23  5053.8 1777.76  5069.9 1777.31  5085.5 1778.72  5144.6 1797.07
  5224.6 1832.81  5256.2 1847.91  5259.4 1848.38  5284.5 1859.22  5308.5 1867.58
#Mann= 9 ,-1 , 0
  4400.4     .07       0  4409.8    .035       0  4510.4      .1       0
  4662.2     .07       0  4938.7    .035       0  4992.3    .035       0
  5012.2    .035       0  5016.2    .035       0  5069.9      .1       0
Bank Sta=5012.2,5016.2
XS Rating Curve= 0 ,0
Exp/Cntr=0.3,0.1

Type RM Length L Ch R = 1 ,32031   ,438,438,438
BEGIN DESCRIPTION:
Stream0040 54.0
END DESCRIPTION:
XS GIS Cut Line= 3
      1952571.04     13917300.28        1952675.       13916725.
      1952724.99     13916425.03
#Sta/Elev= 30
  4415.3 1864.21  4416.6 1863.78  4437.3 1855.65  4458.7 1849.97    4516 1832.13
  4528.8 1828.19    4541 1826.09  4556.2 1822.02  4615.4 1811.05  4647.7 1804.68
  4714.8 1796.59  4766.6 1789.28  4814.1 1786.13  4894.6 1777.29  4909.9  1773.4
    4919 1772.16    4948 1772.94  4976.9 1772.24    5000 1769.18  5000.2 1768.68
    5004 1769.18  5012.9 1769.34  5016.5 1769.43  5028.7 1775.77  5043.9 1781.14
  5102.8 1788.14  5165.6 1794.79  5202.1 1802.13    5269 1823.17    5304 1835.36
#Mann= 11 ,-1 , 0
  4415.3    .035       0  4416.6     .07       0    4516      .1       0
  4615.4     .07       0  4714.8    .035       0  4814.1     .07       0
    4948    .035       0    5000    .035       0    5004    .035       0
  5012.9     .07       0  5102.8      .1       0
Bank Sta=5000,5004
XS Rating Curve= 0 ,0
Exp/Cntr=0.3,0.1

Type RM Length L Ch R = 1 ,31593   ,446,446,446
BEGIN DESCRIPTION:
Stream0040 53.0
END DESCRIPTION:
XS GIS Cut Line= 4
       1953018.6     13917257.26      1953072.42     13916879.59
        1952975.       13916725.      1952787.19     13916344.22
#Sta/Elev= 30
  4435.8 1828.69  4550.6 1818.85    4584 1814.89  4610.8 1808.01  4665.8 1803.06
  4699.1 1798.14  4771.8 1793.64  4780.9 1791.55  4824.1 1787.09  4895.3  1780.5
  4969.8 1775.64  4976.9 1773.66  4983.9 1765.67  4992.7 1764.06    4993 1763.56
  4996.7 1764.06  5001.3 1765.95  5011.6  1767.3  5028.2 1768.01  5058.4 1767.16
  5088.9 1767.08    5112 1770.92  5144.7  1772.6    5177 1772.65  5204.2 1775.58
  5229.8 1784.88  5272.5 1809.17  5308.2 1826.25  5382.9 1856.14  5424.6 1870.47
#Mann= 5 ,-1 , 0
  4435.8    .035       0  4824.1     .07       0  4992.7     .05       0
  4996.7     .07       0  5058.4      .1       0
Bank Sta=4992.7,4996.7
XS Rating Curve= 0 ,0
Exp/Cntr=0.3,0.1

Type RM Length L Ch R = 1 ,31147   ,405,405,405
BEGIN DESCRIPTION:
Stream0040 52.0
END DESCRIPTION:
XS GIS Cut Line= 3
      1953389.25     13917338.89        1953225.       13916375.
      1953165.97     13916172.61
#Sta/Elev= 30
  4030.1 1803.79  4127.8 1796.59    4140 1793.06  4168.6  1788.1  4189.4 1792.57
    4205 1793.12  4264.7 1791.33  4325.6 1792.99  4383.4 1790.19  4390.8 1791.65
  4447.3 1790.63  4598.7 1782.72  4733.4 1775.25  4808.3 1764.86  4847.8  1761.8
  4964.3 1762.03  5001.3 1760.04  5001.5 1759.54  5005.3 1760.04  5005.9 1765.23
  5010.4  1774.7  5022.9 1785.02  5038.5 1791.51  5069.8  1808.8  5107.3 1827.64
  5113.5 1832.23    5156 1856.14  5169.8  1862.1  5179.1  1867.6  5218.7 1882.33
#Mann= 6 ,-1 , 0
  4030.1     .07       0  4390.8    .035       0  4598.7     .07       0
  4847.8      .1       0  5001.3     .05       0  5005.3      .1       0
Bank Sta=5001.3,5005.3
XS Rating Curve= 0 ,0
Exp/Cntr=0.3,0.1

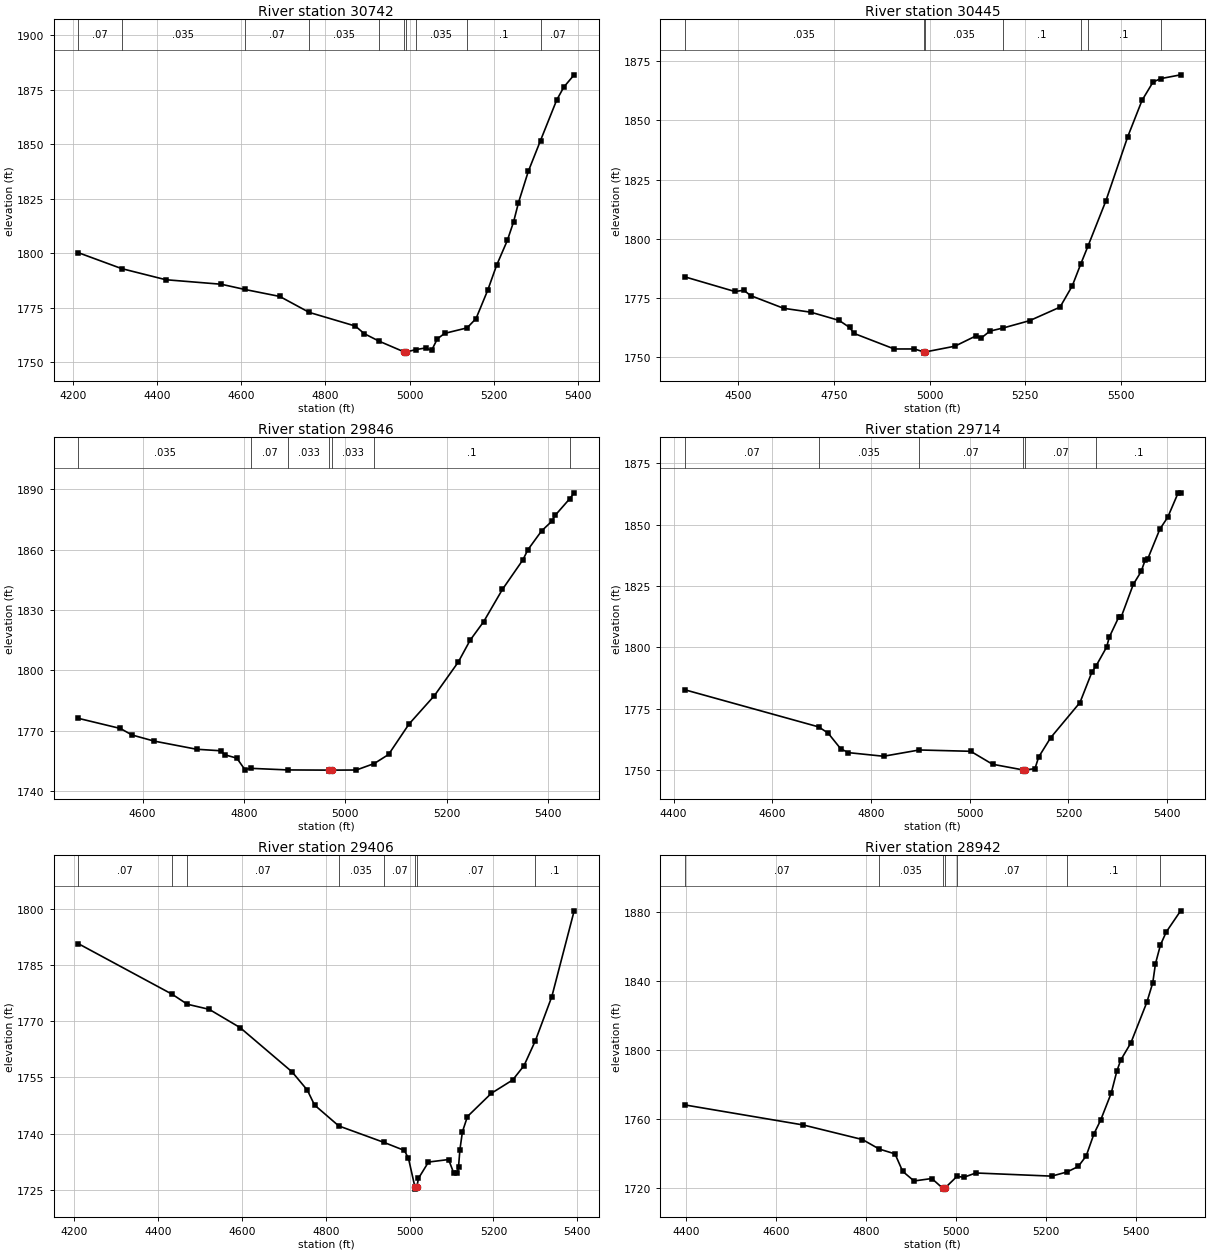
Type RM Length L Ch R = 1 ,30742   ,297,297,297
BEGIN DESCRIPTION:
Stream0040 51.0
END DESCRIPTION:
XS GIS Cut Line= 3
        1953730.     13917146.33        1953575.       13916375.
      1953324.98     13916074.97
#Sta/Elev= 30
  4213.3 1800.28    4316 1792.98  4421.1 1787.87  4552.7  1785.8  4608.2 1783.42
  4691.5 1780.21  4761.6 1772.88  4870.9 1766.63  4892.3 1763.12  4927.7 1759.66
  4987.6  1754.7  4987.9  1754.2  4991.6  1754.7  5014.1  1755.8    5038 1756.57
  5052.1 1755.46  5065.7 1760.73  5082.9 1763.25  5136.3 1765.78  5157.5 1770.01
  5185.2 1782.97  5206.3 1794.41    5232 1805.93  5246.9  1814.5  5258.3 1823.18
  5281.7 1837.58  5310.7 1851.73  5349.2 1870.34  5366.2 1876.29  5390.6 1881.87
#Mann= 10 ,-1 , 0
  4213.3     .07       0    4316    .035       0  4608.2     .07       0
  4761.6    .035       0  4927.7     .07       0  4987.6     .05       0
  4991.6     .07       0  5014.1    .035       0  5136.3      .1       0
  5310.7     .07       0
Bank Sta=4987.6,4991.6
XS Rating Curve= 0 ,0
Exp/Cntr=0.3,0.1

Type RM Length L Ch R = 1 ,30445   ,599,599,599
BEGIN DESCRIPTION:
Mapping XS 872f0353
END DESCRIPTION:
XS GIS Cut Line= 4
      1953832.31     13916956.27      1953836.65     13916387.68
      1953793.25      13916153.3      1953363.59     13915918.94
#Sta/Elev= 30
  4359.6 1783.99  4490.3 1777.81  4514.3 1778.32  4531.4  1776.1  4617.9 1770.72
  4689.2 1769.07  4763.3  1765.6  4790.3 1762.64  4802.3 1760.11  4907.3 1753.56
    4960 1753.57  4984.3 1752.31  4984.5 1751.81  4988.3 1752.31  5065.7 1754.73
  5120.5 1759.05    5135 1758.21  5157.1 1761.08  5192.7 1762.45  5261.1  1765.5
  5340.7 1771.22  5372.7 1780.18  5394.5 1789.25  5413.5 1796.84  5460.4 1815.96
  5517.6 1843.05  5555.2 1858.47  5583.9 1866.15  5603.5 1867.58    5656  1869.2
#Mann= 7 ,-1 , 0
  4359.6    .035       0  4984.3    .035       0  4988.3    .035       0
  5192.7      .1       0  5394.5     .07       0  5413.5      .1       0
  5603.5     .07       0
Bank Sta=4984.3,4988.3
XS Rating Curve= 0 ,0
Exp/Cntr=0.3,0.1

Type RM Length L Ch R = 1 ,29846   ,132,132,132
BEGIN DESCRIPTION:
Stream0040 50.0
END DESCRIPTION:
XS GIS Cut Line= 3
      1953925.03     13916874.97        1954275.       13916475.
      1954475.01     13916074.98
#Sta/Elev= 30
  4473.2 1776.24  4556.2  1771.2    4579 1767.98  4622.5 1764.95  4706.6 1760.89
  4754.1 1760.13    4762 1758.16    4786 1756.47  4801.9  1750.8    4814  1751.4
    4887 1750.61  4968.6 1750.52  4968.9 1750.02    4973 1750.52  5021.9 1750.57
  5057.3 1753.79  5085.6 1758.29  5125.9 1773.39  5176.2 1787.56  5223.1 1804.16
  5246.6 1815.05  5273.4  1824.3  5310.3 1840.27  5350.6  1854.9  5360.7 1860.01
  5387.5 1869.28  5407.6 1874.06  5414.3 1877.02  5443.4 1885.36  5451.9 1888.23
#Mann= 7 ,-1 , 0
  4473.2    .035       0    4814     .07       0    4887    .033       0
  4968.6    .033       0    4973    .033       0  5057.3      .1       0
  5443.4     .07       0
Bank Sta=4968.6,4973
XS Rating Curve= 0 ,0
Exp/Cntr=0.3,0.1

Type RM Length L Ch R = 1 ,29714   ,308,308,308
BEGIN DESCRIPTION:
Stream0040 D5
END DESCRIPTION:
XS GIS Cut Line= 4
      1954193.36     13917116.82      1954330.08     13916734.87
      1954353.95     13916602.49      1954525.38     13916170.67
#Sta/Elev= 30
  4422.6 1782.71  4693.9 1767.58    4713 1765.05  4738.4  1758.7  4753.8  1757.1
  4825.4 1755.62  4897.8 1758.18    5002 1757.64  5046.2 1752.36  5107.8 1750.06
  5108.1 1749.56  5112.2 1750.06  5132.2 1750.56  5139.7 1755.29    5164 1763.17
  5223.4  1777.5  5247.7 1789.95  5255.9 1792.37  5277.4 1800.09  5282.9 1804.18
  5301.7 1812.17  5307.1 1812.43  5331.4 1825.61  5347.4  1830.9  5355.7 1835.63
  5361.1 1836.19  5385.4  1848.2  5401.2 1852.96  5422.4 1862.95  5427.4 1862.95
#Mann= 6 ,-1 , 0
  4422.6     .07       0  4693.9    .035       0  4897.8     .07       0
  5107.8     .05       0  5112.2     .07       0  5255.9      .1       0
Bank Sta=5107.8,5112.2
XS Rating Curve= 0 ,0
Exp/Cntr=0.3,0.1

Type RM Length L Ch R = 1 ,29406   ,464,464,464
BEGIN DESCRIPTION:
Stream0040 49.0
END DESCRIPTION:
XS GIS Cut Line= 3
      1954276.56     13917426.31        1954625.       13916725.
        1954625.       13916325.
#Sta/Elev= 30
  4209.4  1790.7  4433.3 1777.19  4469.3 1774.53  4521.7 1773.16  4595.4 1768.28
  4719.4 1756.46  4755.8 1751.59    4773 1747.61  4830.8 1742.03  4938.9 1737.62
  4987.4 1735.48  4997.2 1733.34  5012.7 1725.65    5013 1725.15  5017.1 1725.65
  5020.9 1728.01  5044.9 1732.38  5092.9 1733.05  5104.9 1729.52  5113.9 1729.47
  5116.6 1731.11  5119.9  1735.7  5125.9 1740.47  5137.9 1744.54  5194.9 1750.74
  5245.9 1754.31  5272.9 1758.14  5300.1 1764.82  5339.2 1776.56  5392.5 1799.47
#Mann= 8 ,-1 , 0
  4209.4     .07       0  4433.3    .035       0  4469.3     .07       0
  4830.8    .035       0  4938.9     .07       0  5012.7     .05       0
  5017.1     .07       0  5300.1      .1       0
Bank Sta=5012.7,5017.1
XS Rating Curve= 0 ,0
Exp/Cntr=0.3,0.1

Type RM Length L Ch R = 1 ,28942   ,456,456,456
BEGIN DESCRIPTION:
Stream0040 48.0
END DESCRIPTION:
XS GIS Cut Line= 3
      1955482.28     13916918.92        1955025.       13916525.
      1954724.97     13916124.97
#Sta/Elev= 30
  4396.8 1768.18  4660.5 1756.53  4792.2 1748.07  4829.5 1742.55  4864.7 1739.73
  4881.7 1729.61    4907    1724  4946.6 1725.42    4971 1719.76  4971.3 1719.26
  4975.4 1719.76  5002.6 1726.66    5018 1726.16  5044.6 1728.64  5213.4 1726.81
  5247.7 1729.24  5272.5 1732.41  5290.2 1738.53  5307.5 1751.38  5322.3 1759.29
  5345.9 1775.02  5358.7 1788.03  5367.1 1794.25  5389.6 1804.19  5425.2  1827.8
  5438.4 1839.17  5444.4 1850.22  5455.5 1861.12  5468.4 1868.66  5500.4 1880.95
#Mann= 7 ,-1 , 0
  4396.8     .07       0  4829.5    .035       0    4971    .035       0
  4975.4    .035       0  5002.6     .07       0  5247.7      .1       0
  5455.5     .07       0
Bank Sta=4971,4975.4
XS Rating Curve= 0 ,0
Exp/Cntr=0.3,0.1

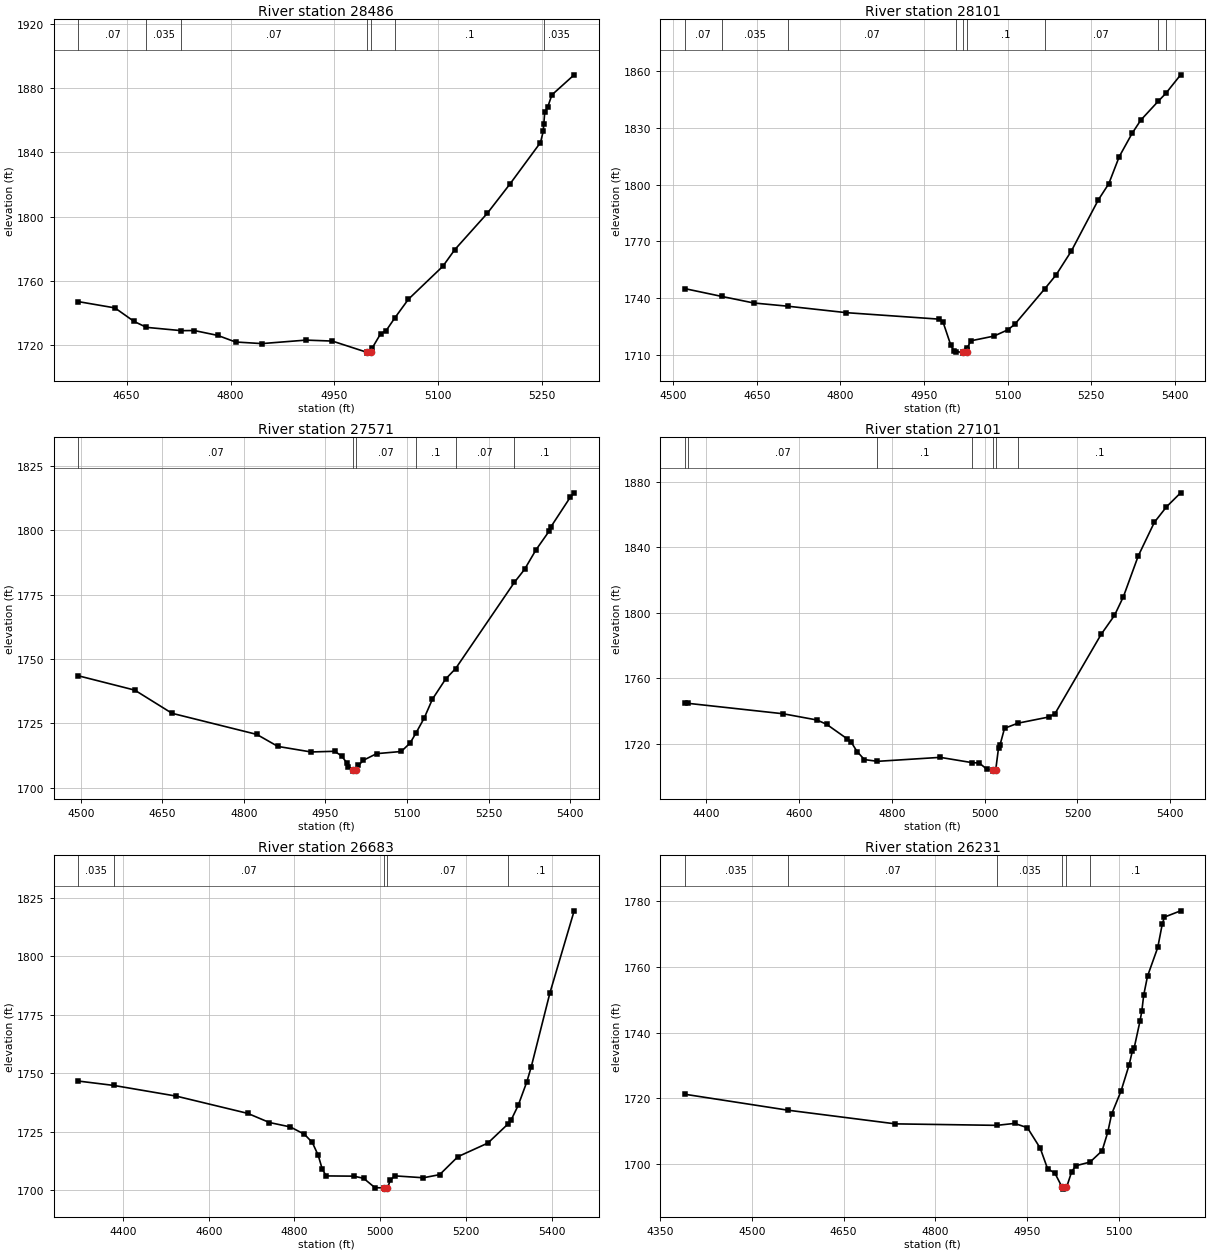
Type RM Length L Ch R = 1 ,28486   ,385,385,385
BEGIN DESCRIPTION:
Stream0040 47.0
END DESCRIPTION:
XS GIS Cut Line= 3
      1955475.02     13916425.02        1955175.       13916125.
      1954925.03     13915975.02
#Sta/Elev= 30
  4580.3 1746.92  4633.1    1743  4660.7 1734.58  4678.7 1730.87  4729.2 1728.81
  4747.6  1728.9  4781.6 1725.84  4807.2 1721.75  4845.2 1720.74  4908.8 1722.92
    4947 1722.32    4997  1715.3  4997.5  1714.8  5003.3  1715.3  5004.4 1717.88
  5016.6 1726.78  5024.8 1728.91  5037.2 1736.76  5056.9 1748.44  5106.5 1768.94
  5123.9  1779.4  5170.5 1801.89  5203.4 1820.25  5247.5 1846.14  5251.5 1853.18
  5252.3 1857.74  5253.6 1864.95    5258 1868.34  5263.9 1875.82  5296.1 1888.35
#Mann= 7 ,-1 , 0
  4580.3     .07       0  4678.7    .035       0  4729.2     .07       0
    4997     .05       0  5003.3     .07       0  5037.2      .1       0
  5252.3    .035       0
Bank Sta=4997,5003.3
XS Rating Curve= 0 ,0
Exp/Cntr=0.3,0.1

Type RM Length L Ch R = 1 ,28101   ,530,530,530
BEGIN DESCRIPTION:
Stream0040 46.0
END DESCRIPTION:
XS GIS Cut Line= 3
      1955738.03     13916372.23      1955472.87     13915949.02
      1955172.89     13915699.04
#Sta/Elev= 30
  4520.8 1744.91  4587.2 1740.78  4644.3 1737.32  4705.6 1735.61  4810.7 1732.19
  4977.8 1728.75  4984.1 1727.39  4998.3 1714.91    5004 1711.96    5008 1711.49
  5020.3 1711.28  5020.8 1710.78  5026.7 1711.28  5026.9 1712.68  5027.7 1713.44
  5034.1 1717.29  5075.6 1719.79  5100.2 1723.06  5112.9 1725.98  5166.5 1744.69
  5187.1 1752.13  5214.4 1764.71    5263 1791.87  5281.8 1800.44  5300.5 1814.73
  5323.7 1827.11  5339.4 1834.15  5370.2 1843.96  5384.2 1848.25  5410.7 1858.04
#Mann= 9 ,-1 , 0
  4520.8     .07       0  4587.2    .035       0  4705.6     .07       0
    5008      .1       0  5020.3     .05       0  5026.7      .1       0
  5166.5     .07       0  5370.2    .035       0  5384.2     .07       0
Bank Sta=5020.3,5026.7
XS Rating Curve= 0 ,0
Exp/Cntr=0.3,0.1

Type RM Length L Ch R = 1 ,27571   ,470,470,470
BEGIN DESCRIPTION:
Stream0040 45.0
END DESCRIPTION:
XS GIS Cut Line= 3
      1956064.75     13916214.27        1955925.       13915725.
      1955975.01     13915324.95
#Sta/Elev= 30
  4495.4 1743.51  4599.1 1737.95  4667.7 1728.94  4823.6 1720.74  4862.4 1716.07
  4923.5 1713.91  4966.8 1714.18  4979.7 1712.37  4989.1  1709.7  4992.2 1707.96
  4999.8 1706.97  5000.3 1706.47  5006.5 1706.97  5010.7  1708.7  5019.8  1710.7
    5044 1713.26  5089.3  1714.1  5105.6 1717.36  5116.2 1721.18  5131.6  1727.1
  5146.7 1734.43  5170.9 1742.23  5189.3  1746.3  5297.6 1779.86  5316.1 1784.83
  5337.2 1792.45  5361.4 1799.72  5364.4 1801.31  5400.1 1812.84  5407.4  1814.6
#Mann= 6 ,-1 , 0
  4495.4     .07       0  4999.8     .05       0  5006.5     .07       0
  5116.2      .1       0  5189.3     .07       0  5297.6      .1       0
Bank Sta=4999.8,5006.5
XS Rating Curve= 0 ,0
Exp/Cntr=0.3,0.1

Type RM Length L Ch R = 1 ,27101   ,418,418,418
BEGIN DESCRIPTION:
Stream0040 44.0
END DESCRIPTION:
XS GIS Cut Line= 3
      1956137.45     13916238.92        1956325.       13915625.
      1956474.99     13915225.03
#Sta/Elev= 30
  4353.5 1745.28  4361.3 1744.78  4565.4 1738.44  4638.4 1734.63  4659.3    1732
  4703.1 1723.22  4712.5 1720.99    4725 1715.35  4740.7 1710.46  4768.8 1709.38
  4904.2 1711.81  4972.5  1708.6  4988.5 1708.34  5004.4 1704.65  5017.1  1703.9
  5017.6  1703.4  5023.8  1703.9    5030 1717.65  5033.2 1719.39  5042.9 1729.56
    5072  1732.7    5139 1736.49  5151.8 1738.55  5251.1 1786.88    5280 1798.51
  5299.2 1809.91  5331.2  1834.8    5366 1855.37  5392.1 1864.81  5422.6 1873.37
#Mann= 7 ,-1 , 0
  4353.5    .035       0  4361.3     .07       0  4768.8      .1       0
  4972.5     .07       0  5017.1     .05       0  5023.8     .07       0
    5072      .1       0
Bank Sta=5017.1,5023.8
XS Rating Curve= 0 ,0
Exp/Cntr=0.3,0.1

Type RM Length L Ch R = 1 ,26683   ,452,452,452
BEGIN DESCRIPTION:
Stream0040 43.0
END DESCRIPTION:
XS GIS Cut Line= 3
      1956137.23     13916287.45        1956675.       13915825.
      1956875.01     13915424.98
#Sta/Elev= 30
  4295.9 1746.68  4378.9  1744.8  4524.2 1740.24  4690.9 1732.86  4741.5 1728.95
  4790.4 1727.05  4823.3 1723.91  4841.7  1720.4  4855.5 1714.88  4864.7 1709.08
  4873.9  1706.1  4938.3    1706  4961.3 1705.08  4987.6 1701.09    5010 1700.95
  5010.5 1700.45  5016.8 1700.95  5023.5 1704.15  5033.6 1706.13  5100.7 1705.31
  5138.7 1706.65  5181.2 1714.32  5251.2 1720.16    5297 1728.13  5305.3 1729.97
    5322 1736.33  5342.1  1746.4  5352.2 1752.67  5395.8 1784.34  5452.4  1819.5
#Mann= 5 ,-1 , 0
  4295.9    .035       0  4378.9     .07       0    5010     .05       0
  5016.8     .07       0    5297      .1       0
Bank Sta=5010,5016.8
XS Rating Curve= 0 ,0
Exp/Cntr=0.3,0.1

Type RM Length L Ch R = 1 ,26231   ,469,469,469
BEGIN DESCRIPTION:
Stream0040 42.0
END DESCRIPTION:
XS GIS Cut Line= 3
      1957045.55     13916329.97        1957025.       13915725.
      1956974.99     13915524.97
#Sta/Elev= 30
    4390 1721.29  4558.6 1716.44  4734.7 1712.27  4900.8 1711.82  4929.7 1712.41
  4950.7 1711.11  4971.7 1704.88  4983.7 1698.63  4995.7 1697.28  5007.7  1692.9
  5008.2  1692.4  5014.7  1692.9  5023.1 1697.65  5029.8 1699.51  5053.3 1700.64
    5073 1704.08  5082.3 1709.76  5088.5 1715.21    5104 1722.28  5117.1 1730.16
  5122.5 1734.43  5125.6  1735.5  5134.9 1743.47    5138 1746.61  5141.1  1751.5
  5147.3 1757.23  5164.1    1766  5171.5 1773.16  5175.1 1775.24  5201.5 1777.14
#Mann= 6 ,-1 , 0
    4390    .035       0  4558.6     .07       0  4900.8    .035       0
  5007.7    .035       0  5014.7    .035       0  5053.3      .1       0
Bank Sta=5007.7,5014.7
XS Rating Curve= 0 ,0
Exp/Cntr=0.3,0.1