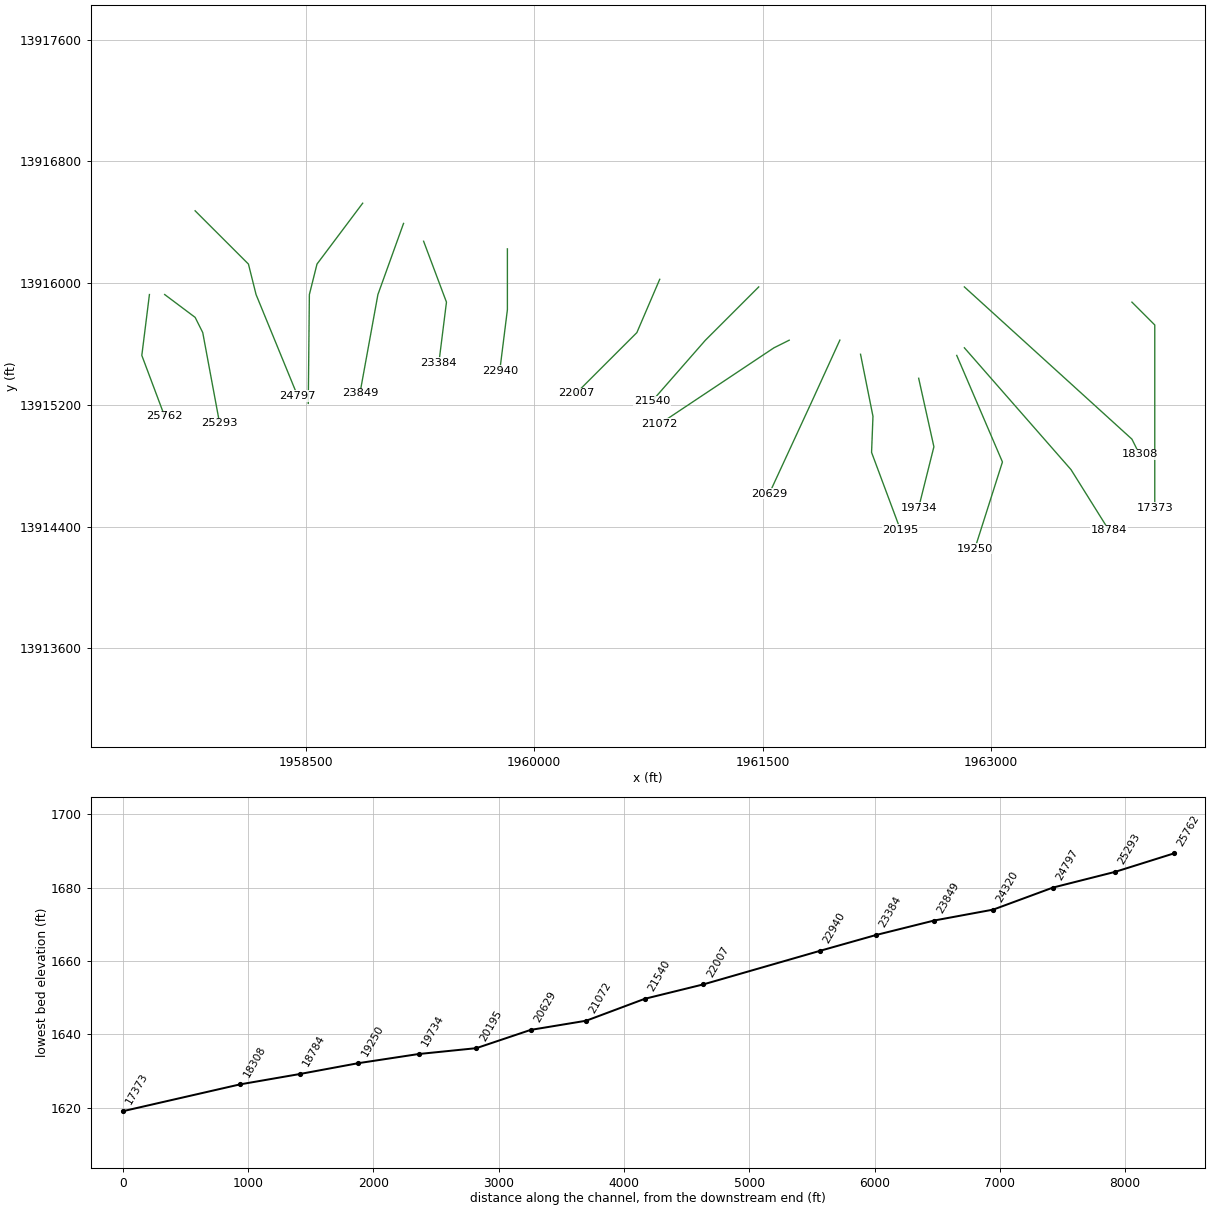
HEC-RAS study Stream0040.prj: Stream0040 Base Level Engineering

--- Stream0040.g01 (geometry) --- (continued)

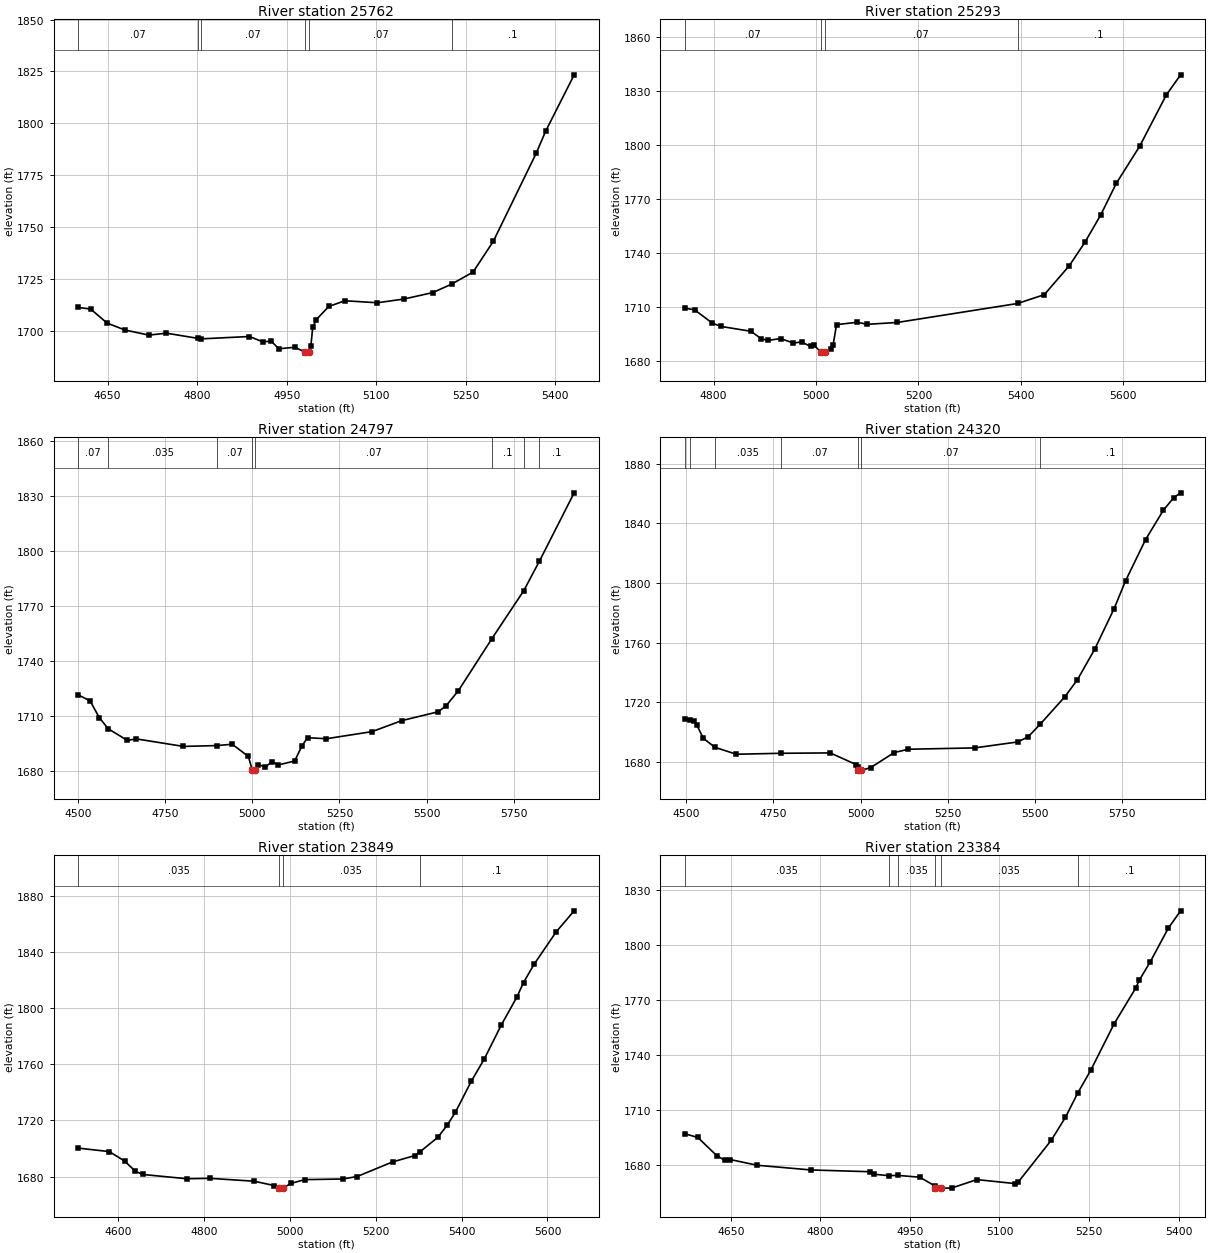
Type RM Length L Ch R = 1 ,25762   ,469,469,469
BEGIN DESCRIPTION:
Stream0040 41.0
END DESCRIPTION:
XS GIS Cut Line= 3
        1957475.     13915925.02        1957425.       13915525.
      1957574.99     13915125.04
#Sta/Elev= 30
  4601.1 1711.31  4621.7 1710.54  4649.2 1703.79  4678.8 1700.47  4719.1 1697.98
  4748.7 1698.91  4801.7 1696.39  4807.1 1696.18  4887.7 1697.31  4909.9 1694.74
    4924 1695.08  4936.8 1691.41  4963.7 1692.12  4980.9  1689.8  4981.4  1689.3
  4988.1  1689.8  4990.5 1692.74  4993.6 1701.74  4999.6 1705.45  5020.6 1711.79
  5047.4 1714.53  5101.9 1713.57  5146.7 1715.38  5194.8 1718.49  5226.2 1722.54
  5262.1 1728.36  5295.9 1743.11  5367.8 1785.57  5383.8 1796.32  5431.4 1823.38
#Mann= 6 ,-1 , 0
  4601.1     .07       0  4801.7    .035       0  4807.1     .07       0
  4980.9     .05       0  4988.1     .07       0  5226.2      .1       0
Bank Sta=4980.9,4988.1
XS Rating Curve= 0 ,0
Exp/Cntr=0.3,0.1

Type RM Length L Ch R = 1 ,25293   ,496,496,496
BEGIN DESCRIPTION:
Stream0040 40.0
END DESCRIPTION:
XS GIS Cut Line= 4
      1957575.03     13915924.98        1957775.       13915775.
        1957825.       13915675.      1957935.79     13915078.98
#Sta/Elev= 30
  4743.9 1709.25  4762.9 1708.36  4797.9 1700.88  4815.3 1699.08  4872.9 1696.41
  4892.9 1692.33  4905.4 1691.33  4931.1 1692.34    4956 1689.88  4971.8 1690.48
  4989.7 1687.97  4996.6  1688.6  5009.7 1684.77  5010.2 1684.27    5017 1684.77
  5030.1 1686.33  5033.4 1688.66  5040.1 1700.12  5080.4 1701.41  5100.5 1700.29
    5159 1701.33  5393.8 1711.88  5445.8 1716.78  5494.6 1732.89  5525.1 1745.91
  5555.7 1760.96  5586.2 1778.59  5631.9 1799.26    5684  1827.8  5711.9 1838.97
#Mann= 4 ,-1 , 0
  4743.9     .07       0  5009.7     .05       0    5017     .07       0
  5393.8      .1       0
Bank Sta=5009.7,5017
XS Rating Curve= 0 ,0
Exp/Cntr=0.3,0.1

Type RM Length L Ch R = 1 ,24797   ,477,477,477
BEGIN DESCRIPTION:
Stream0040 39.0
END DESCRIPTION:
XS GIS Cut Line= 4
      1957775.02     13916474.98        1958125.       13916125.
        1958175.       13915925.      1958448.14     13915258.28
#Sta/Elev= 30
  4501.2 1721.62  4535.2  1718.3  4561.1 1709.23  4586.8 1703.15  4641.8 1696.75
  4667.2  1697.6  4802.5 1693.49  4899.2 1693.95  4942.5 1694.67  4988.6 1688.01
  5000.1 1680.49  5000.6 1679.99  5007.5 1680.49  5016.2 1683.59  5037.8 1682.25
  5056.4 1685.22  5074.9 1683.38  5121.3 1685.51  5142.9 1693.95  5158.4 1698.25
  5212.4 1697.68  5343.4 1701.57  5428.4 1707.57  5532.3 1712.37    5555 1715.54
  5590.7 1723.86  5687.2 1752.41  5778.2  1778.5  5822.8 1794.51  5922.8 1831.97
#Mann= 8 ,-1 , 0
  4501.2     .07       0  4586.8    .035       0  4899.2     .07       0
  5000.1     .05       0  5007.5     .07       0  5687.2      .1       0
  5778.2     .07       0  5822.8      .1       0
Bank Sta=5000.1,5007.5
XS Rating Curve= 0 ,0
Exp/Cntr=0.3,0.1

Type RM Length L Ch R = 1 ,24320   ,471,471,471
BEGIN DESCRIPTION:
Stream0040 38.0
END DESCRIPTION:
XS GIS Cut Line= 4
      1958874.97     13916524.96        1958575.       13916125.
        1958525.       13915925.      1958517.74     13915210.04
#Sta/Elev= 30
    4496 1708.93  4512.3 1708.09  4522.7 1707.37  4530.2    1705  4548.9    1696
  4582.4 1689.92  4643.8 1685.29  4772.9 1685.94  4912.7 1686.18  4987.9 1678.29
  4992.2 1677.05  4992.8 1674.48  4993.3 1673.98    5002 1674.48  5028.7 1676.34
  5096.4 1686.44  5136.6 1688.64  5326.6 1689.54  5450.5 1693.54  5480.5 1697.05
    5515 1705.49  5585.5 1723.88  5621.5 1735.26  5671.1 1755.77  5726.5 1782.88
  5759.5  1801.6  5816.5 1829.01  5867.6 1848.77  5897.6 1857.23  5917.1 1860.42
#Mann= 7 ,-1 , 0
    4496    .035       0  4512.3     .07       0  4582.4    .035       0
  4772.9     .07       0  4992.8     .05       0    5002     .07       0
    5515      .1       0
Bank Sta=4992.8,5002
XS Rating Curve= 0 ,0
Exp/Cntr=0.3,0.1

Type RM Length L Ch R = 1 ,23849   ,465,465,465
BEGIN DESCRIPTION:
Stream0040 37.0
END DESCRIPTION:
XS GIS Cut Line= 3
       1959143.2     13916392.04        1958975.       13915925.
      1958857.24     13915277.53
#Sta/Elev= 30
  4507.7 1700.22  4579.9 1697.73  4615.6 1690.96  4640.8 1683.67  4657.9 1681.44
  4760.4 1678.41  4814.3 1678.69  4917.5 1676.63  4963.1 1673.58  4974.4 1671.51
  4974.9 1671.01  4983.7 1671.51  5001.9 1675.02    5035 1677.78  5123.5 1678.22
    5157    1680  5239.3 1690.38  5291.2  1694.9  5303.2  1697.6  5344.8  1707.9
  5366.6 1716.56  5385.7 1725.74  5422.5 1747.77  5452.8 1763.63  5492.4 1787.82
    5529 1807.92  5544.3 1818.14  5568.6 1831.04  5620.5 1854.31  5662.2 1869.23
#Mann= 4 ,-1 , 0
  4507.7    .035       0  4974.4    .035       0  4983.7    .035       0
  5303.2      .1       0
Bank Sta=4974.4,4983.7
XS Rating Curve= 0 ,0
Exp/Cntr=0.3,0.1

Type RM Length L Ch R = 1 ,23384   ,444,444,444
BEGIN DESCRIPTION:
Stream0040 36.0
END DESCRIPTION:
XS GIS Cut Line= 3
      1959274.99     13916275.03        1959425.       13915875.
      1959375.01     13915475.04
#Sta/Elev= 30
  4573.1 1697.25  4594.9 1695.23    4627 1685.19  4639.8 1682.82  4649.4 1683.17
  4694.3 1680.07    4784 1677.51  4883.3 1676.54  4889.7 1675.19  4914.9 1674.39
  4929.9 1674.55  4966.6 1673.54  4992.2 1668.74  4992.4 1667.55  4992.9 1667.05
  5001.7 1667.55  5020.1 1667.66  5062.2 1672.25  5125.7 1670.09  5131.8 1671.04
  5186.8 1693.72  5210.4 1706.14  5231.4 1719.63  5252.7 1731.76    5292 1757.18
  5328.3 1776.76  5334.3 1781.05  5352.5 1790.98  5382.7 1809.34  5403.4 1818.83
#Mann= 6 ,-1 , 0
  4573.1    .035       0  4914.9     .07       0  4929.9    .035       0
  4992.4    .035       0  5001.7    .035       0  5231.4      .1       0
Bank Sta=4992.4,5001.7
XS Rating Curve= 0 ,0
Exp/Cntr=0.3,0.1

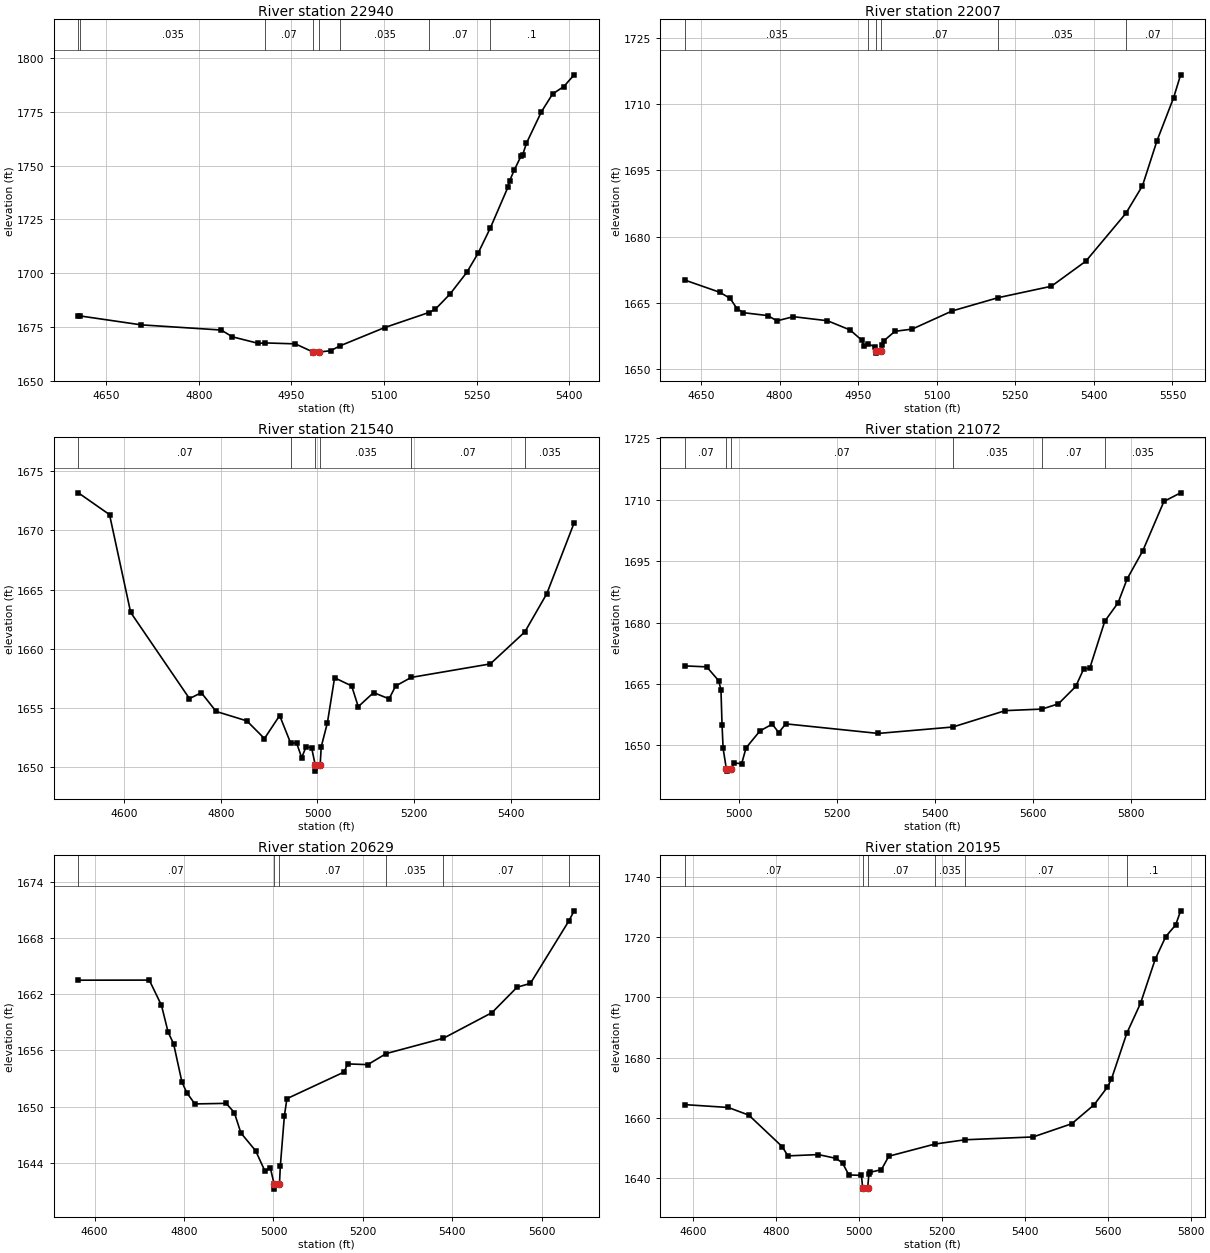
Type RM Length L Ch R = 1 ,22940   ,933,933,933
BEGIN DESCRIPTION:
Stream0040 35.0
END DESCRIPTION:
XS GIS Cut Line= 3
        1959825.     13916224.96        1959825.       13915825.
        1959775.     13915424.97
#Sta/Elev= 30
  4604.8  1680.2  4607.3 1680.09  4706.5 1675.93  4836.2 1673.52  4854.2 1670.37
  4896.2 1667.32  4907.8 1667.52  4956.2 1667.08  4985.1 1663.27  4985.6 1662.77
  4994.6 1663.27  5013.3 1663.88    5029  1666.2  5100.9 1674.66  5172.4 1681.66
  5182.6 1683.08  5206.8 1690.25    5234 1700.35  5252.1 1709.16    5272 1720.94
  5300.5  1739.9  5303.5 1743.06  5310.8 1747.91  5321.6 1754.34  5324.7  1755.2
  5330.7 1760.51  5354.9 1775.12    5373  1783.4  5391.2 1786.85  5407.9 1792.29
#Mann= 8 ,-1 , 0
  4604.8     .07       0  4607.3    .035       0  4907.8     .07       0
  4985.1     .05       0  4994.6     .07       0    5029    .035       0
  5172.4     .07       0    5272      .1       0
Bank Sta=4985.1,4994.6
XS Rating Curve= 0 ,0
Exp/Cntr=0.3,0.1

Type RM Length L Ch R = 1 ,22007   ,467,467,467
BEGIN DESCRIPTION:
Stream0040 34.0
END DESCRIPTION:
XS GIS Cut Line= 3
      1960824.99     13916024.99        1960675.       13915675.
      1960274.97     13915274.97
#Sta/Elev= 30
  4619.1 1670.14  4685.9 1667.37  4705.5 1666.01  4718.6  1663.7  4731.1 1662.75
  4777.3  1662.1  4795.1 1660.91  4826.3 1661.85  4891.5 1660.93  4934.5 1658.85
  4956.8 1656.54  4961.9 1655.16  4969.3 1655.65  4982.9 1655.01  4984.5  1654.1
    4985  1653.6  4994.5  1654.1    4996 1655.53  4999.3 1656.42  5020.3 1658.54
  5053.2 1659.04  5129.5 1663.15  5216.9 1666.14  5318.9 1668.74  5384.6 1674.41
    5461 1685.23  5492.8  1691.5  5520.4 1701.64  5552.2 1711.42  5565.6  1716.6
#Mann= 6 ,-1 , 0
  4619.1    .035       0  4969.3     .07       0  4984.5     .05       0
  4994.5     .07       0  5216.9    .035       0    5461     .07       0
Bank Sta=4984.5,4994.5
XS Rating Curve= 0 ,0
Exp/Cntr=0.3,0.1

Type RM Length L Ch R = 1 ,21540   ,468,468,468
BEGIN DESCRIPTION:
Stream0040 33.0
END DESCRIPTION:
XS GIS Cut Line= 3
        1961475.       13915975.        1961125.       13915625.
      1960774.99     13915224.99
#Sta/Elev= 30
  4504.9 1673.17  4569.5 1671.33  4613.2 1663.08    4735  1655.8  4759.5  1656.3
  4790.1 1654.72  4853.8 1653.92  4890.2 1652.43  4921.7 1654.37  4944.4 1652.05
  4956.8 1652.05  4967.4 1650.81  4975.9  1651.7  4987.8 1651.67  4995.4 1650.18
  4995.9 1649.68  5005.5 1650.18  5007.8 1651.74  5020.5 1653.75  5035.4 1657.56
  5070.8 1656.87  5084.4 1655.12  5116.2 1656.31  5148.2 1655.78  5161.9 1656.87
  5194.1 1657.59  5357.8 1658.73  5429.3 1661.43  5474.8 1664.66  5531.4 1670.64
#Mann= 6 ,-1 , 0
  4504.9     .07       0  4944.4    .035       0  4995.4    .035       0
  5005.5    .035       0  5194.1     .07       0  5429.3    .035       0
Bank Sta=4995.4,5005.5
XS Rating Curve= 0 ,0
Exp/Cntr=0.3,0.1

Type RM Length L Ch R = 1 ,21072   ,443,443,443
BEGIN DESCRIPTION:
Stream0040 32.0
END DESCRIPTION:
XS GIS Cut Line= 3
      1961674.98     13915624.99        1961575.       13915575.
      1960824.97     13915074.98
#Sta/Elev= 30
  4888.5 1669.41  4933.3 1669.17  4957.9 1665.76  4962.4 1663.49  4964.6 1655.06
  4966.8 1649.23  4973.5  1644.2    4974  1643.7  4983.8  1644.2  4989.2 1645.68
  5004.7 1645.52  5013.7 1649.39    5042 1653.51  5067.2 1655.18  5080.4 1653.12
  5094.8 1655.25  5283.8 1652.91  5436.3 1654.48  5543.4 1658.48  5618.3 1658.86
  5651.9 1660.14  5687.4 1664.39  5703.4 1668.61  5716.2 1668.91  5746.7 1680.32
  5773.9 1684.82  5792.5 1690.69  5824.4 1697.53  5867.6 1709.59  5901.7 1711.69
#Mann= 6 ,-1 , 0
  4888.5     .07       0  4973.5     .05       0  4983.8     .07       0
  5436.3    .035       0  5618.3     .07       0  5746.7    .035       0
Bank Sta=4973.5,4983.8
XS Rating Curve= 0 ,0
Exp/Cntr=0.3,0.1

Type RM Length L Ch R = 1 ,20629   ,434,434,434
BEGIN DESCRIPTION:
Stream0040 31.0
END DESCRIPTION:
XS GIS Cut Line= 3
      1962007.68     13915625.49        1961825.       13915225.
      1961544.38     13914617.68
#Sta/Elev= 30
  4563.5 1663.49  4722.2  1663.5  4749.4 1660.82  4764.4 1657.94  4776.6 1656.71
  4795.3 1652.62    4806  1651.5  4824.1 1650.29  4894.2 1650.35  4912.4 1649.37
  4927.2 1647.19  4960.2 1645.29  4980.4 1643.18  4993.2 1643.43  5001.7  1641.7
  5002.2  1641.2  5013.4  1641.7  5015.4 1643.68  5024.4 1648.99  5030.1 1650.85
  5158.4  1653.7  5165.8 1654.56    5211 1654.48  5252.1 1655.66  5380.4  1657.3
  5488.9 1660.03    5545 1662.74  5574.8 1663.15  5660.6 1669.79  5672.7 1670.89
#Mann= 6 ,-1 , 0
  4563.5     .07       0  5001.7     .05       0  5013.4     .07       0
  5252.1    .035       0  5380.4     .07       0  5660.6    .035       0
Bank Sta=5001.7,5013.4
XS Rating Curve= 0 ,0
Exp/Cntr=0.3,0.1

Type RM Length L Ch R = 1 ,20195   ,461,461,461
BEGIN DESCRIPTION:
Stream0040 30.0
END DESCRIPTION:
XS GIS Cut Line= 4
      1962143.36     13915532.55        1962225.       13915125.
       1962215.8     13914887.89      1962405.49     13914379.04
#Sta/Elev= 30
  4579.9 1664.33  4684.9 1663.38  4734.3 1660.84  4814.6 1650.39  4828.7 1647.28
  4902.2 1647.71    4945 1646.44  4960.3 1644.91  4975.6 1640.95    5006 1640.79
  5008.8 1636.72  5009.3 1636.22    5021 1636.72    5024 1641.21  5026.5 1641.81
    5054 1642.69    5072 1647.17  5183.3 1651.22  5256.2 1652.64  5420.1 1653.58
  5513.4 1657.98  5567.2 1664.28  5599.2 1670.14  5608.8 1672.73  5646.1 1688.09
  5679.3 1698.07  5714.5 1712.66  5740.1 1720.25  5763.9 1724.09  5775.9  1728.8
#Mann= 6 ,-1 , 0
  4579.9     .07       0  5008.8     .05       0    5021     .07       0
  5183.3    .035       0  5256.2     .07       0  5646.1      .1       0
Bank Sta=5008.8,5021
XS Rating Curve= 0 ,0
Exp/Cntr=0.3,0.1

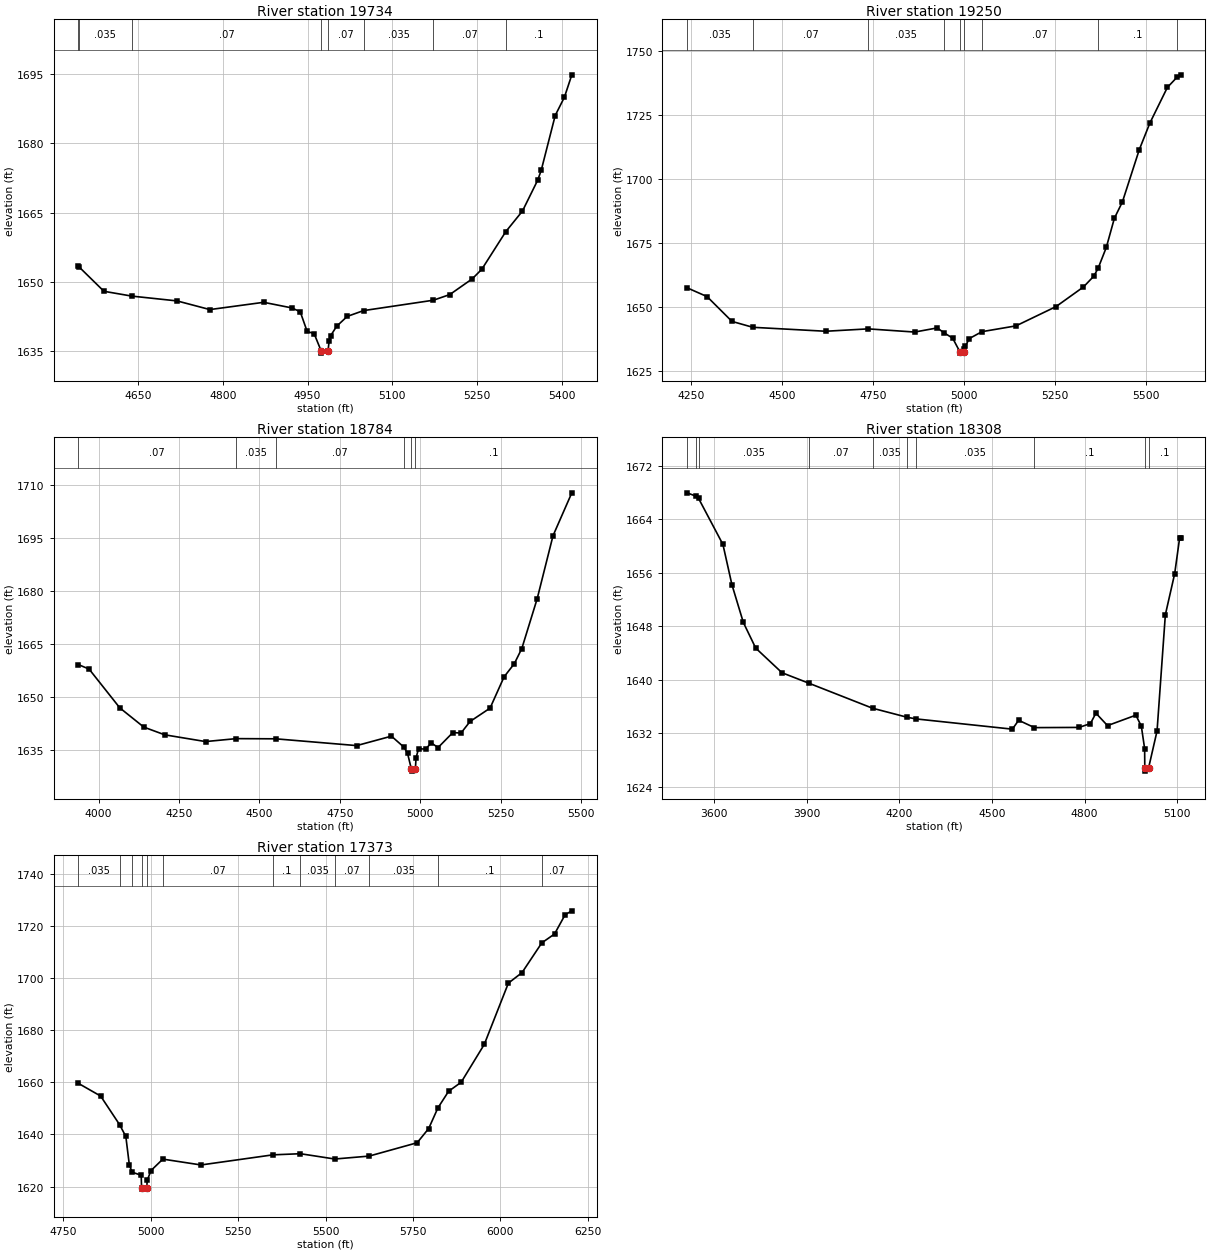
Type RM Length L Ch R = 1 ,19734   ,484,484,484
BEGIN DESCRIPTION:
Stream0040 29.0
END DESCRIPTION:
XS GIS Cut Line= 3
      1962525.01     13915374.96        1962625.       13914925.
      1962525.01     13914525.04
#Sta/Elev= 30
  4544.3 1653.44  4545.5 1653.28  4589.8 1647.98  4639.1 1646.94  4719.2  1645.9
  4777.2 1644.03  4872.4  1645.6  4921.7  1644.4    4937 1643.57  4949.3  1639.3
  4961.6 1638.84    4974 1635.12  4974.5 1634.62  4986.2 1635.12  4988.3 1637.34
  4990.9  1638.4  5001.6 1640.44  5020.1 1642.55  5049.1 1643.81  5172.5 1646.05
  5201.6 1647.27  5241.2 1650.66  5258.2 1652.73  5300.7 1660.87  5330.2 1665.32
  5357.2 1672.01  5363.4 1674.13  5388.1 1685.96  5404.4 1689.92  5417.5 1694.75
#Mann= 8 ,-1 , 0
  4544.3     .07       0  4545.5    .035       0  4639.1     .07       0
    4974     .05       0  4986.2     .07       0  5049.1    .035       0
  5172.5     .07       0  5300.7      .1       0
Bank Sta=4974,4986.2
XS Rating Curve= 0 ,0
Exp/Cntr=0.3,0.1

Type RM Length L Ch R = 1 ,19250   ,466,466,466
BEGIN DESCRIPTION:
Stream0040 28.0
END DESCRIPTION:
XS GIS Cut Line= 3
      1962774.99     13915525.02        1963075.       13914825.
      1962894.16     13914256.58
#Sta/Elev= 30
  4238.3 1657.58  4293.2 1654.15  4361.7 1644.48  4419.1 1642.18  4619.6 1640.64
  4736.3 1641.57  4864.4 1640.33  4926.4 1641.94  4944.5  1640.1  4968.8 1637.96
  4988.8 1632.61  4989.3 1632.11  5001.1 1632.61  5001.4 1633.75  5004.1 1634.81
  5014.3 1637.76  5049.5 1640.48  5143.1 1642.74  5253.2 1650.25  5328.8 1657.92
  5357.1  1662.1  5369.1 1665.21  5391.7 1673.37  5413.8  1684.7  5435.9 1691.08
  5482.4 1711.48  5511.4 1721.81  5559.6 1735.72    5587 1739.83  5596.4 1740.64
#Mann= 9 ,-1 , 0
  4238.3    .035       0  4419.1     .07       0  4736.3    .035       0
  4944.5      .1       0  4988.8     .05       0  5001.1      .1       0
  5049.5     .07       0  5369.1      .1       0    5587     .07       0
Bank Sta=4988.8,5001.1
XS Rating Curve= 0 ,0
Exp/Cntr=0.3,0.1

Type RM Length L Ch R = 1 ,18784   ,476,476,476
BEGIN DESCRIPTION:
Stream0040 27.0
END DESCRIPTION:
XS GIS Cut Line= 3
      1962825.02     13915574.97        1963525.       13914775.
      1963775.01     13914374.98
#Sta/Elev= 30
  3936.5 1659.31  3970.3 1658.02  4065.9 1647.04  4140.4 1641.61  4205.4 1639.43
  4332.4 1637.52    4428 1638.35  4550.3  1638.3  4802.3 1636.38  4910.4 1639.05
    4950 1635.87  4960.5 1634.17  4972.5 1629.66    4973 1629.16  4984.8 1629.66
  4986.8 1632.91  4994.7 1635.49  5016.5 1635.39  5034.2 1637.14  5055.4 1635.83
  5101.4 1640.08  5126.5 1639.91  5154.8  1643.2    5217 1646.98  5260.6 1655.83
  5292.4 1659.55  5315.7 1663.83  5363.6 1677.96  5412.7 1695.73  5471.2 1707.87
#Mann= 6 ,-1 , 0
  3936.5     .07       0    4428    .035       0  4550.3     .07       0
    4950      .1       0  4972.5     .05       0  4984.8      .1       0
Bank Sta=4972.5,4984.8
XS Rating Curve= 0 ,0
Exp/Cntr=0.3,0.1

Type RM Length L Ch R = 1 ,18308   ,935,935,935
BEGIN DESCRIPTION:
Stream0040 26.0
END DESCRIPTION:
XS GIS Cut Line= 3
        1962825.       13915975.        1963925.       13914975.
        1963975.     13914875.01
#Sta/Elev= 30
  3513.1 1667.92  3540.3 1667.44  3550.1 1667.09    3629 1660.21  3658.1  1654.2
  3695.1 1648.55  3735.2 1644.72  3820.3 1641.04  3908.8 1639.45  4113.4 1635.74
  4226.2 1634.38  4254.7 1634.14  4566.3 1632.61  4586.6 1633.94  4637.7 1632.84
  4782.2 1632.87    4819 1633.44  4836.8    1635  4874.4 1633.14  4966.2  1634.7
  4983.9 1633.06  4994.6  1629.7  4995.1 1626.84  4995.6 1626.34  5007.5 1626.84
  5034.8 1632.34  5061.7 1649.71  5091.9 1655.84  5107.7 1661.11  5111.5 1661.12
#Mann= 10 ,-1 , 0
  3513.1    .035       0  3540.3     .07       0  3550.1    .035       0
  3908.8     .07       0  4113.4    .035       0  4226.2     .07       0
  4254.7    .035       0  4637.7      .1       0  4995.1     .05       0
  5007.5      .1       0
Bank Sta=4995.1,5007.5
XS Rating Curve= 0 ,0
Exp/Cntr=0.3,0.1

Type RM Length L Ch R = 1 ,17373   ,469,469,469
BEGIN DESCRIPTION:
Stream0040 25.0
END DESCRIPTION:
XS GIS Cut Line= 3
      1963924.99     13915875.01        1964075.       13915725.
        1964075.     13914525.04
#Sta/Elev= 30
  4792.5 1659.63  4856.6 1654.73  4910.9 1643.75  4928.7 1639.22  4938.8 1628.25
  4946.8 1625.52  4972.7 1624.35  4973.7 1619.53  4974.2 1619.03  4988.7 1619.53
  4989.7 1622.34  5000.8 1626.17  5034.6 1630.54  5143.8  1628.3  5349.5 1632.18
  5428.1 1632.61  5526.4 1630.58  5624.8  1631.7  5762.1 1636.82  5795.1 1642.27
  5821.5 1650.18  5852.1 1656.56  5888.1 1660.03  5954.1 1674.53  6023.1 1698.04
  6062.1 1702.07  6118.8 1713.49  6155.1 1716.88  6185.4 1724.26  6204.6 1725.77
#Mann= 12 ,-1 , 0
  4792.5    .035       0  4910.9     .07       0  4946.8      .1       0
  4973.7     .05       0  4988.7      .1       0  5034.6     .07       0
  5349.5      .1       0  5428.1    .035       0  5526.4     .07       0
  5624.8    .035       0  5821.5      .1       0  6118.8     .07       0
Bank Sta=4973.7,4988.7
XS Rating Curve= 0 ,0
Exp/Cntr=0.3,0.1