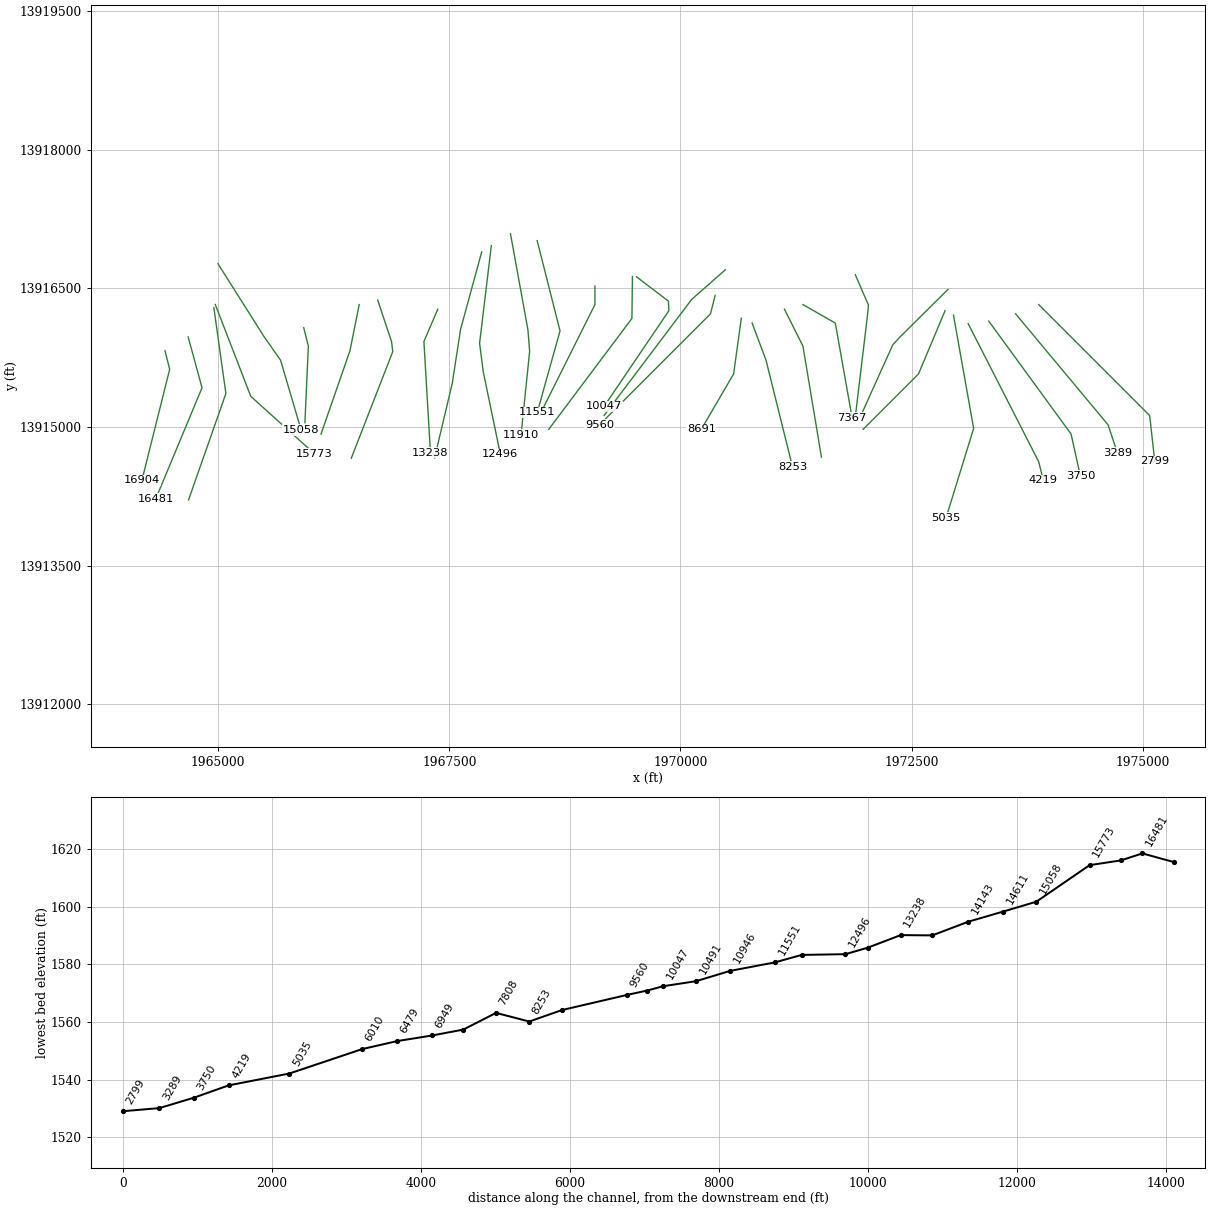
HEC-RAS study Stream0040.prj: Stream0040 Base Level Engineering

--- Stream0040.g01 (geometry) --- (continued)

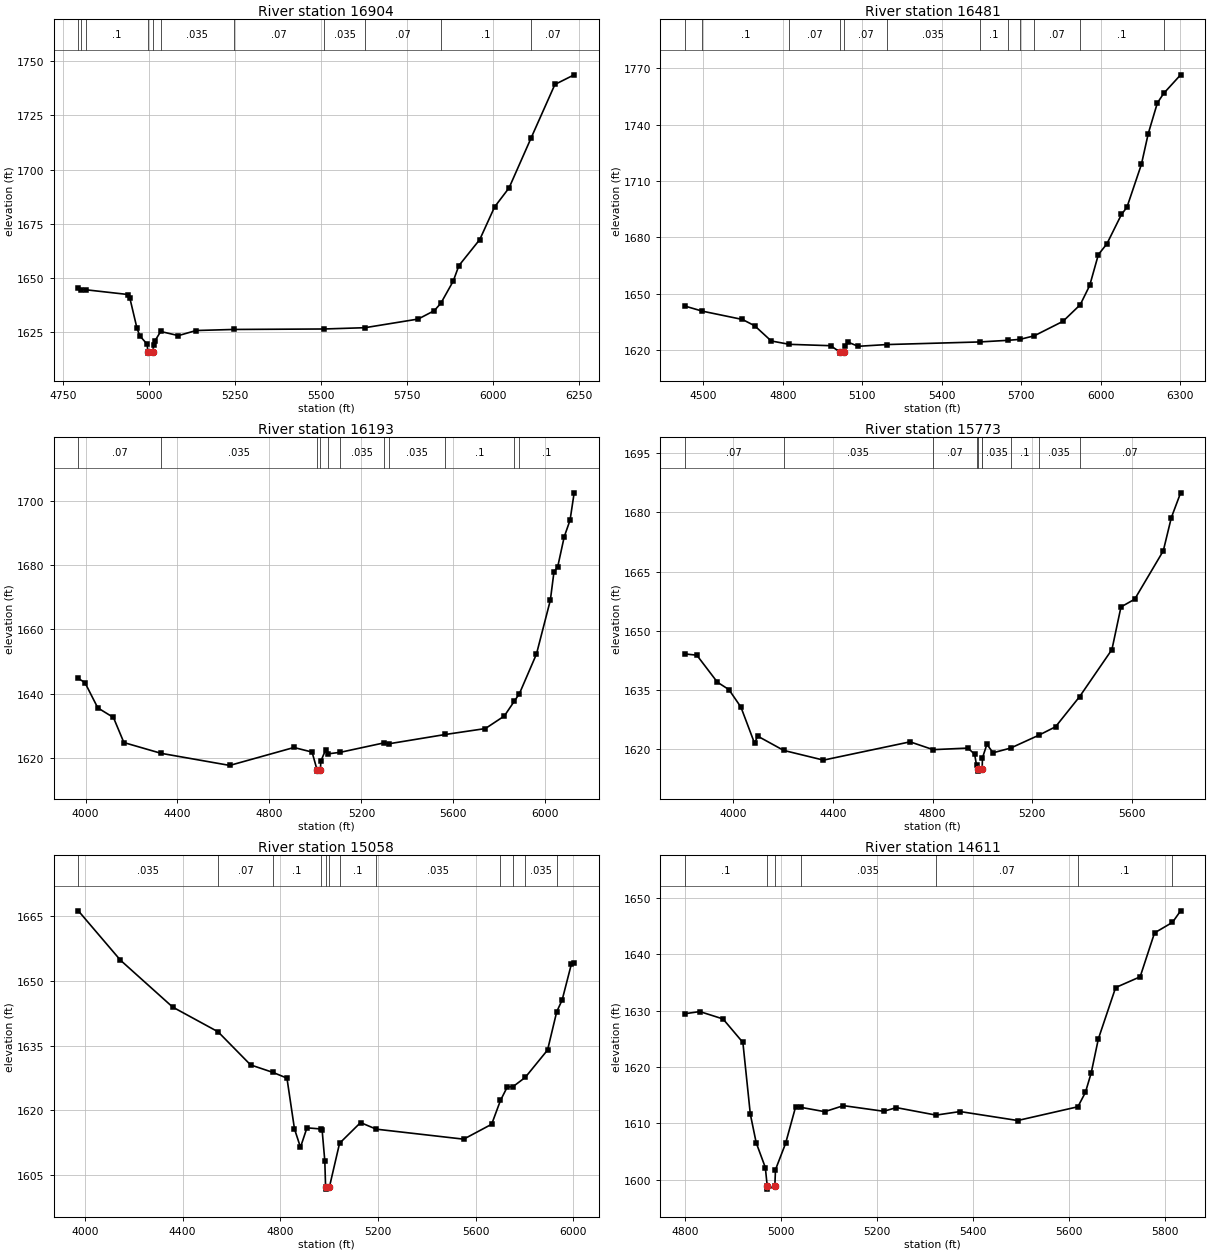
Type RM Length L Ch R = 1 ,16904   ,423,423,423
BEGIN DESCRIPTION:
Stream0040 24.0
END DESCRIPTION:
XS GIS Cut Line= 3
      1964424.99     13915825.04        1964475.       13915625.
      1964175.01     13914425.02
#Sta/Elev= 30
  4793.8 1645.25    4801 1644.75  4814.9 1644.67  4938.6 1642.47  4943.8  1640.8
  4964.4    1627  4972.6 1623.45  4994.3 1619.56    4996 1615.98  4996.5 1615.48
    5011 1615.98  5012.8 1619.21  5015.9 1620.92  5033.5 1625.44    5085 1623.55
  5136.5 1625.89  5245.8 1626.38  5509.7  1626.6    5628 1627.19  5782.8 1631.17
  5829.7 1635.02  5848.9 1638.45  5884.8  1648.6  5901.4 1655.77  5962.2 1667.79
  6005.4 1682.82  6047.4 1691.56  6110.9 1714.32  6180.9 1739.21  6236.9 1743.64
#Mann= 11 ,-1 , 0
  4793.8    .035       0    4801     .07       0  4814.9      .1       0
    4996     .05       0    5011      .1       0  5033.5    .035       0
  5245.8     .07       0  5509.7    .035       0    5628     .07       0
  5848.9      .1       0  6110.9     .07       0
Bank Sta=4996,5011
XS Rating Curve= 0 ,0
Exp/Cntr=0.3,0.1

Type RM Length L Ch R = 1 ,16481   ,288,288,288
BEGIN DESCRIPTION:
Stream0040 23.0
END DESCRIPTION:
XS GIS Cut Line= 3
      1964674.99     13915975.04        1964825.       13915425.
      1964325.01     13914225.03
#Sta/Elev= 30
  4430.4 1643.52  4496.6  1640.8  4647.7 1636.39  4694.1 1633.02  4756.4 1624.95
  4825.1 1623.16  4980.2 1622.44  5016.8 1618.99  5017.3 1618.49  5031.8 1618.99
  5033.5 1622.22  5047.6 1624.25    5084 1622.12  5191.9 1623.04    5542 1624.43
  5649.9  1625.3  5694.6 1625.81  5748.4 1627.69  5856.8  1635.4  5921.8  1644.2
  5957.6 1654.46  5990.3 1670.89  6022.3 1676.55  6077.3 1692.19    6098 1696.03
  6152.6 1718.84  6178.3 1735.11  6212.7 1751.43  6236.5 1756.53  6300.5 1766.42
#Mann= 12 ,-1 , 0
  4430.4     .07       0  4496.6      .1       0  4825.1     .07       0
  5016.8     .05       0  5031.8     .07       0  5191.9    .035       0
    5542      .1       0  5649.9     .07       0  5694.6      .1       0
  5748.4     .07       0  5921.8      .1       0  6236.5     .07       0
Bank Sta=5016.8,5031.8
XS Rating Curve= 0 ,0
Exp/Cntr=0.3,0.1

Type RM Length L Ch R = 1 ,16193   ,420,420,420
BEGIN DESCRIPTION:
Mapping XS 15523aef
END DESCRIPTION:
XS GIS Cut Line= 3
      1964952.93     13916291.83      1965083.14       13915363.
      1964679.48     13914212.79
#Sta/Elev= 30
  3968.7  1644.8  3997.2 1643.54  4053.4 1635.68  4121.4  1632.7  4166.9 1624.92
  4328.8 1621.58  4627.3 1617.83  4906.6 1623.39  4985.5 1621.97  5006.7 1616.56
  5007.2 1616.06  5021.8 1616.56  5023.6 1619.13  5044.9 1622.73    5055 1621.42
  5108.5  1621.9  5298.9 1624.83  5318.7 1624.53  5565.6 1627.43  5739.2 1629.26
  5821.7 1633.15  5865.7 1637.79  5887.1 1640.04  5961.6 1652.37    6022 1669.08
  6037.9 1677.93  6053.8 1679.37  6082.4 1688.75  6107.8 1693.93  6125.6 1702.39
#Mann= 11 ,-1 , 0
  3968.7     .07       0  4328.8    .035       0  5006.7    .035       0
  5021.8    .035       0    5055     .07       0  5108.5    .035       0
  5298.9     .07       0  5318.7    .035       0  5565.6      .1       0
  5865.7     .07       0  5887.1      .1       0
Bank Sta=5006.7,5021.8
XS Rating Curve= 0 ,0
Exp/Cntr=0.3,0.1

Type RM Length L Ch R = 1 ,15773   ,715,715,715
BEGIN DESCRIPTION:
Mapping XS 15c43aa9
END DESCRIPTION:
XS GIS Cut Line= 3
      1964968.14      13916326.5      1965352.23     13915332.62
        1966038.     13914714.13
#Sta/Elev= 30
    3806 1644.12  3854.2  1643.8  3936.8 1636.95  3982.8 1635.09  4031.1 1630.65
  4085.7  1621.5  4098.6 1623.28  4202.7 1619.67  4362.3 1617.21  4709.7 1621.84
  4802.2 1619.86  4941.8 1620.26  4968.7 1618.69  4976.4 1615.87  4983.3 1614.92
  4983.8 1614.42  4998.8 1614.92  5000.1 1617.79  5017.9 1621.21  5042.6 1619.07
    5113 1620.26  5225.5  1623.5  5293.1 1625.65  5389.6 1633.28  5519.4 1645.22
  5555.7 1656.02  5610.8 1657.99  5725.4 1670.23  5757.7 1678.65    5795 1684.94
#Mann= 10 ,-1 , 0
    3806     .07       0  4202.7    .035       0  4802.2     .07       0
  4976.4      .1       0  4983.3     .05       0  4998.8      .1       0
  5000.1    .035       0    5113      .1       0  5225.5    .035       0
  5389.6     .07       0
Bank Sta=4983.3,4998.8
XS Rating Curve= 0 ,0
Exp/Cntr=0.3,0.1

Type RM Length L Ch R = 1 ,15058   ,447,447,447
BEGIN DESCRIPTION:
Stream0040 21.1
END DESCRIPTION:
XS GIS Cut Line= 4
        1964997.     13916767.15      1965493.16     13915982.35
      1965674.71     13915723.14      1965896.77     13914968.28
#Sta/Elev= 30
  3972.4 1666.29  4145.1 1654.83  4358.8 1643.97  4544.9 1638.23  4678.2 1630.55
  4770.7 1628.79  4827.3 1627.48  4858.1  1615.7  4882.7 1611.43  4909.2 1615.95
  4966.6 1615.68  4971.4 1615.46  4982.4 1608.27  4985.6 1602.23  4986.1 1601.73
  5001.3 1602.23  5042.9 1612.37  5128.9 1617.17  5193.2 1615.64  5551.5 1613.32
  5666.1 1616.78  5702.2  1622.3  5729.8 1625.39  5753.8 1625.51  5803.8 1627.65
  5895.2    1634  5932.8 1642.89  5954.9 1645.59  5992.4 1653.85  6004.2 1654.15
#Mann= 12 ,-1 , 0
  3972.4    .035       0  4544.9     .07       0  4770.7      .1       0
  4966.6     .07       0  4985.6     .05       0  5001.3     .07       0
  5042.9      .1       0  5193.2    .035       0  5702.2     .07       0
  5753.8      .1       0  5803.8    .035       0  5932.8     .07       0
Bank Sta=4985.6,5001.3
XS Rating Curve= 0 ,0
Exp/Cntr=0.3,0.1

Type RM Length L Ch R = 1 ,14611   ,468,468,468
BEGIN DESCRIPTION:
Stream0040 21.0
END DESCRIPTION:
XS GIS Cut Line= 3
      1965924.99     13916075.04        1965975.       13915875.
        1965938.     13915048.23
#Sta/Elev= 30
  4799.2 1629.46  4830.6 1629.84  4878.9 1628.53  4920.3 1624.36  4935.8 1611.63
  4948.1 1606.53  4967.1 1602.14  4971.1  1598.8  4971.6  1598.3  4986.9  1598.8
  4988.3 1601.76  5009.3 1606.41  5030.4 1612.96  5041.1 1612.83  5090.9 1612.06
    5130 1613.13    5214 1612.13  5240.3 1612.78    5323 1611.45  5373.2 1612.08
  5493.3 1610.49  5618.8 1612.93  5634.5 1615.49  5646.5 1618.93  5661.5    1625
  5697.5 1634.11  5748.6 1636.02  5778.6 1643.82    5816 1645.69    5833 1647.74
#Mann= 7 ,-1 , 0
  4799.2      .1       0  4971.1     .05       0  4986.9      .1       0
  5041.1    .035       0    5323     .07       0  5618.8      .1       0
    5816     .07       0
Bank Sta=4971.1,4986.9
XS Rating Curve= 0 ,0
Exp/Cntr=0.3,0.1

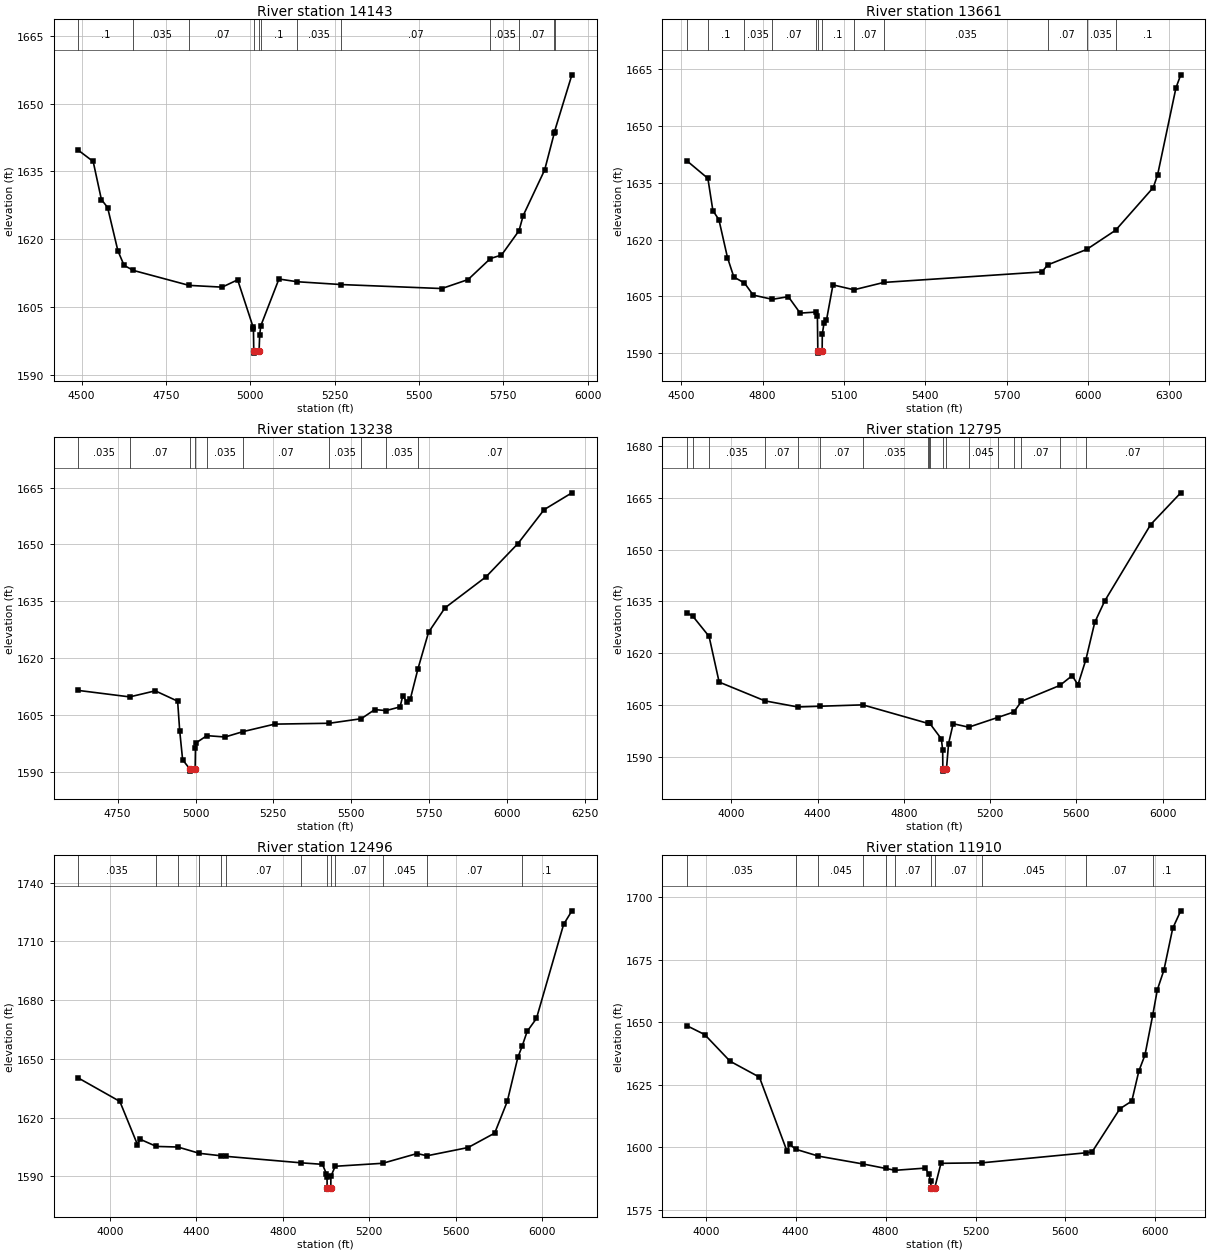
Type RM Length L Ch R = 1 ,14143   ,482,482,482
BEGIN DESCRIPTION:
Stream0040 20.0
END DESCRIPTION:
XS GIS Cut Line= 3
      1966524.99     13916324.97        1966425.       13915825.
      1966111.98     13914924.21
#Sta/Elev= 30
  4490.1 1639.71  4534.4  1637.2  4558.8 1628.78  4577.2 1627.01  4607.8  1617.4
  4626.1  1614.2  4653.6 1613.08  4818.7 1609.77  4916.8 1609.38  4962.7    1611
  5008.9 1600.46  5009.5 1600.13  5010.5 1595.27    5011 1594.77  5026.3 1595.27
    5028 1598.77  5031.3 1600.81  5085.1 1611.18  5138.9 1610.58  5270.4 1609.95
  5567.9 1609.07  5645.9 1611.06  5712.1 1615.72  5744.9 1616.48  5796.8 1621.88
  5809.2 1625.23  5872.8 1635.32    5901  1643.4  5902.1 1643.84  5953.6 1656.39
#Mann= 12 ,-1 , 0
  4490.1      .1       0  4653.6    .035       0  4818.7     .07       0
  5010.5     .05       0  5026.3     .07       0  5031.3      .1       0
  5138.9    .035       0  5270.4     .07       0  5712.1    .035       0
  5796.8     .07       0    5901      .1       0  5902.1     .07       0
Bank Sta=5010.5,5026.3
XS Rating Curve= 0 ,0
Exp/Cntr=0.3,0.1

Type RM Length L Ch R = 1 ,13661   ,423,423,423
BEGIN DESCRIPTION:
Stream0040 19.0
END DESCRIPTION:
XS GIS Cut Line= 4
        1966725.     13916375.01        1966875.       13915925.
      1966887.95     13915815.62      1966439.58     13914663.16
#Sta/Elev= 30
  4521.3 1640.76  4598.1 1636.16  4616.6 1627.65  4638.8 1625.26  4670.4 1615.26
  4693.8 1610.13  4733.1 1608.54  4765.3 1605.36  4835.7 1604.24  4894.9 1604.94
  4938.5  1600.6  4996.3 1600.88  5002.1 1599.77  5003.7 1590.54  5004.2 1590.04
  5019.6 1590.54  5020.2 1595.05  5026.3 1597.87  5035.4 1598.68  5059.5 1608.05
  5137.1 1606.76  5247.3  1608.7  5830.2 1611.47  5851.7 1613.33  5995.3  1617.4
  6102.1 1622.47  6241.1 1633.74  6257.2 1637.14  6324.8 1660.05  6342.4 1663.49
#Mann= 12 ,-1 , 0
  4521.3     .07       0  4598.1      .1       0  4733.1    .035       0
  4835.7     .07       0  4996.3      .1       0  5003.7     .05       0
  5019.6      .1       0  5137.1     .07       0  5247.3    .035       0
  5851.7     .07       0  5995.3    .035       0  6102.1      .1       0
Bank Sta=5003.7,5019.6
XS Rating Curve= 0 ,0
Exp/Cntr=0.3,0.1

Type RM Length L Ch R = 1 ,13238   ,443,443,443
BEGIN DESCRIPTION:
Stream0040 18.0
END DESCRIPTION:
XS GIS Cut Line= 3
        1967375.       13916275.        1967225.       13915925.
       1967295.8     13914722.68
#Sta/Elev= 30
  4623.4 1611.45  4788.7 1609.74  4870.8 1611.34  4942.6 1608.61  4949.2 1600.82
  4958.6 1593.15  4982.3 1590.64  4982.8 1590.14  4998.8 1590.64  4999.9 1596.24
    5002 1597.61  5036.5 1599.51  5094.8 1599.15    5153 1600.58  5254.1 1602.55
  5429.9 1602.78  5532.2 1603.98  5575.6 1606.39  5611.8 1606.12  5656.8  1607.1
  5665.8 1610.09  5677.8 1608.46  5689.8 1609.19  5714.4 1617.19  5748.3  1626.8
    5801 1633.24  5933.2 1641.47  6035.4 1650.23  6119.6 1659.19  6208.6 1663.62
#Mann= 10 ,-1 , 0
  4623.4    .035       0  4788.7     .07       0  4982.3     .05       0
  4998.8     .07       0  5036.5    .035       0    5153     .07       0
  5429.9    .035       0  5532.2     .07       0  5611.8    .035       0
  5714.4     .07       0
Bank Sta=4982.3,4998.8
XS Rating Curve= 0 ,0
Exp/Cntr=0.3,0.1

Type RM Length L Ch R = 1 ,12795   ,299,299,299
BEGIN DESCRIPTION:
Stream0040 17.3
END DESCRIPTION:
XS GIS Cut Line= 4
      1967850.28     13916895.15      1967621.94     13916058.38
      1967531.11     13915471.92      1967340.76     13914666.53
#Sta/Elev= 30
  3795.1 1631.62  3820.6 1630.82  3897.1 1624.87  3943.8 1611.61  4156.1 1606.16
  4308.4 1604.39  4411.3  1604.6  4609.7    1605  4912.1 1599.62  4918.3 1599.61
  4920.4 1599.61  4973.9 1595.12    4980 1591.85  4980.8 1586.27  4981.3 1585.77
  4997.4 1586.27  5007.3 1593.73  5028.6 1599.53  5100.5 1598.52  5234.8 1601.33
    5310 1602.93  5345.3 1606.04  5523.1 1610.64  5580.2 1613.47  5607.2 1610.83
  5643.8 1618.13  5684.9 1628.93    5731 1635.13  5944.2 1657.33  6083.5 1666.53
#Mann= 18 ,-1 , 0
  3795.1    .035       0  3820.6     .07       0  3897.1    .035       0
  4156.1     .07       0  4308.4    .045       0  4411.3     .07       0
  4609.7    .035       0  4912.1     .07       0  4918.3    .035       0
  4920.4     .07       0  4980.8     .05       0  4997.4     .07       0
  5100.5    .045       0  5234.8     .07       0    5310    .045       0
  5345.3     .07       0  5523.1    .035       0  5643.8     .07       0
Bank Sta=4980.8,4997.4
XS Rating Curve= 0 ,0
Exp/Cntr=0.3,0.1

Type RM Length L Ch R = 1 ,12496   ,586,586,586
BEGIN DESCRIPTION:
Stream0040 17.2
END DESCRIPTION:
XS GIS Cut Line= 4
      1967954.01     13916961.55      1967827.26     13915906.78
      1967866.87     13915598.35      1968051.44       13914708.
#Sta/Elev= 30
  3854.2 1640.28  4046.6  1628.3  4128.1 1606.27  4140.2    1609  4215.5 1605.32
    4315 1605.02  4414.4  1601.8  4513.9 1600.56  4539.7 1600.24  4882.9 1596.97
  4983.3 1596.18  5001.5 1591.44  5004.5 1589.56  5005.3 1584.03  5005.8 1583.53
  5021.9 1584.03  5022.6 1590.03  5042.2 1595.19  5261.9 1596.72  5421.2  1601.7
  5466.5 1600.54    5657 1604.76  5779.8 1612.12    5838  1628.3    5887 1650.81
  5906.4 1656.37  5929.9 1664.03  5972.8 1670.62  6098.4 1718.63  6136.8 1725.57
#Mann= 13 ,-1 , 0
  3854.2    .035       0  4215.5    .045       0    4315    .035       0
  4414.4     .07       0  4513.9    .035       0  4539.7     .07       0
  4882.9     .07       0  5005.3     .05       0  5021.9     .07       0
  5042.2     .07       0  5261.9    .045       0  5466.5     .07       0
  5906.4      .1       0
Bank Sta=5005.3,5021.9
XS Rating Curve= 0 ,0
Exp/Cntr=0.3,0.1

Type RM Length L Ch R = 1 ,11910   ,359,359,359
BEGIN DESCRIPTION:
Stream0040 17.1
END DESCRIPTION:
XS GIS Cut Line= 4
      1968161.46     13917090.81      1968350.19     13916051.45
      1968368.63      13915819.2      1968275.83     13914917.19
#Sta/Elev= 30
  3916.8 1648.61  3995.3 1645.09  4108.1 1634.44  4238.6 1628.07  4361.2 1598.51
  4373.4 1601.14    4401  1599.2  4501.4 1596.47  4700.2 1593.32  4799.6 1591.56
  4842.2  1590.8    4977 1591.68  4992.1 1589.26  5001.1 1586.34  5001.7 1583.77
  5002.2 1583.27  5018.6 1583.77  5046.3 1593.59  5229.2  1593.8  5690.7  1597.8
  5718.5 1598.14  5842.1  1615.4  5895.2 1618.49  5926.5 1630.48  5953.7 1636.89
  5988.5 1652.95  6008.8 1663.01  6038.1 1670.89  6077.3 1687.61  6112.9  1694.6
#Mann= 11 ,-1 , 0
  3916.8    .035       0    4401     .07       0  4501.4    .045       0
  4700.2     .07       0  4799.6    .045       0  4842.2     .07       0
  5001.7     .05       0  5018.6     .07       0  5229.2    .045       0
  5690.7     .07       0  5988.5      .1       0
Bank Sta=5001.7,5018.6
XS Rating Curve= 0 ,0
Exp/Cntr=0.3,0.1

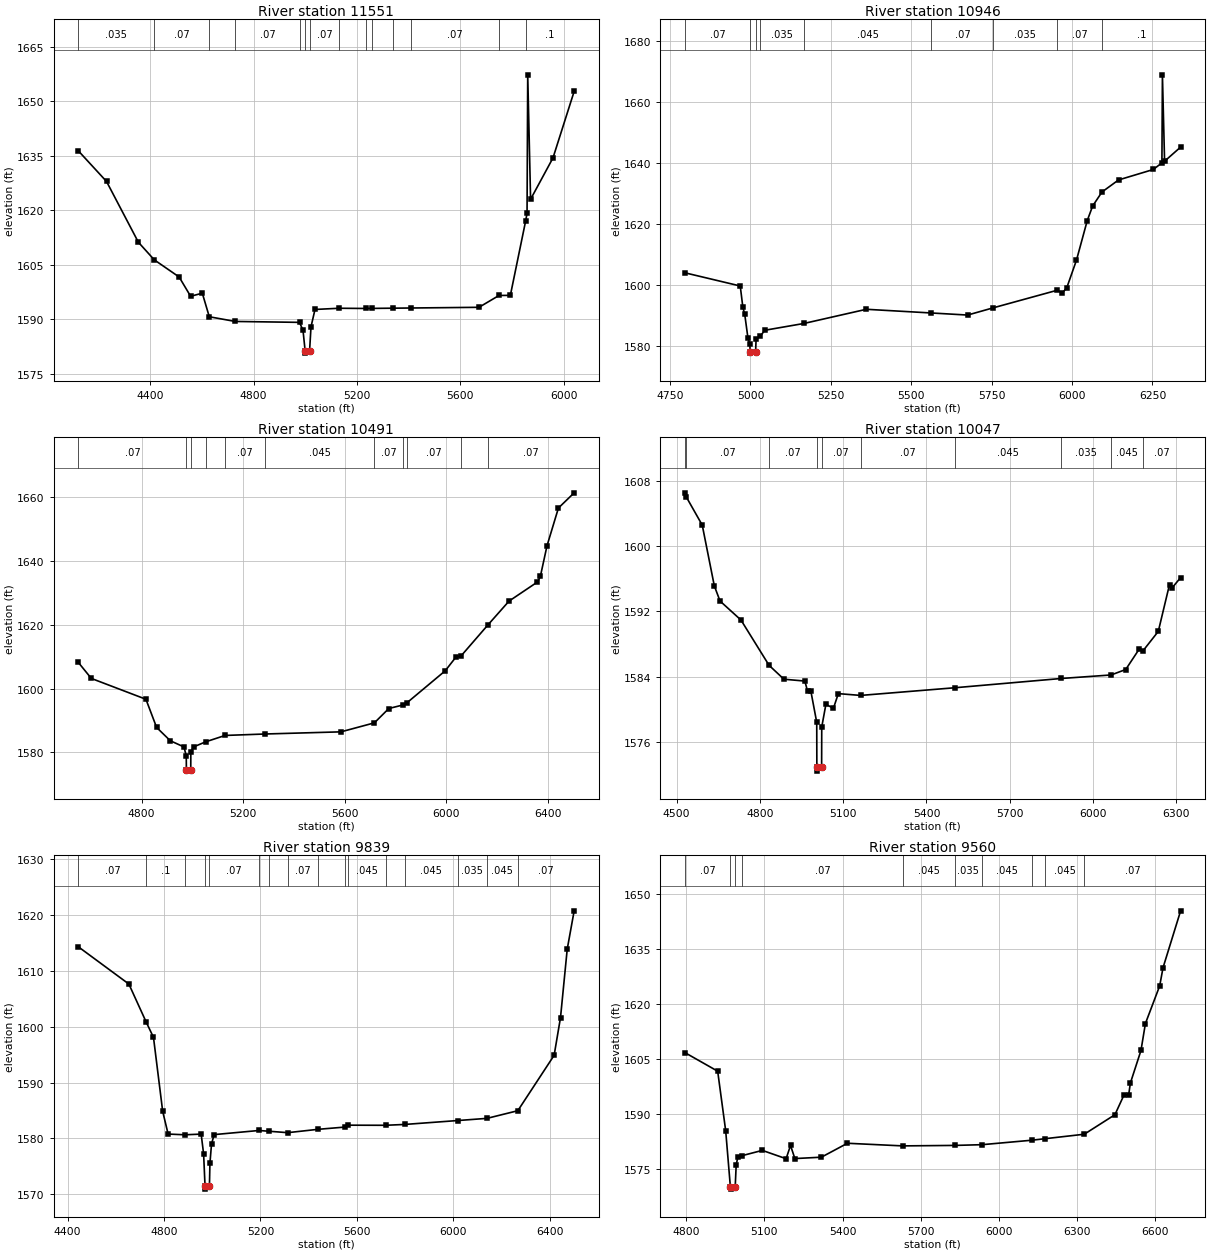
Type RM Length L Ch R = 1 ,11551   ,605,605,605
BEGIN DESCRIPTION:
Mapping XS b2a5ed54
END DESCRIPTION:
XS GIS Cut Line= 3
        1968450.     13917016.88       1968697.4     13916040.14
      1968451.91     13915161.68
#Sta/Elev= 30
  4121.3 1636.32  4230.4  1627.9  4353.8 1611.18  4415.2 1606.35  4511.5 1601.63
  4556.1 1596.32  4601.3 1597.18  4628.3 1590.69    4729  1589.4  4977.7 1589.15
  4991.2 1586.95  4999.6 1581.19  5000.1 1580.69  5016.5 1581.19  5022.2 1587.95
  5037.6  1592.7  5131.7 1593.03  5234.8 1592.97  5258.8 1592.99  5340.7 1593.05
  5408.9  1593.1  5672.5 1593.29  5749.9 1596.54    5794 1596.58    5853 1616.98
  5858.6 1619.16  5861.2 1657.22  5872.3 1622.99  5959.1 1634.39    6041 1652.67
#Mann= 14 ,-1 , 0
  4121.3    .035       0  4415.2     .07       0  4628.3    .035       0
    4729     .07       0  4977.7     .07       0  4999.6     .05       0
  5016.5     .07       0  5131.7     .07       0  5234.8    .045       0
  5258.8     .07       0  5340.7    .045       0  5408.9     .07       0
  5749.9    .035       0    5853      .1       0
Bank Sta=4999.6,5016.5
XS Rating Curve= 0 ,0
Exp/Cntr=0.3,0.1

Type RM Length L Ch R = 1 ,10946   ,455,455,455
BEGIN DESCRIPTION:
Stream0040 17.0
END DESCRIPTION:
XS GIS Cut Line= 3
        1969075.     13916525.03        1969075.       13916325.
      1968474.99     13915124.97
#Sta/Elev= 30
  4795.8 1604.03  4968.2  1599.7  4976.2 1592.84  4982.2 1590.38  4992.2 1582.61
    4998 1580.69  4998.9 1578.21  4999.4 1577.71    5016 1578.21  5017.5 1582.37
  5030.8 1583.31  5044.6  1585.2  5165.9 1587.42  5360.3 1592.07  5562.5 1590.86
  5675.1 1590.18  5755.5 1592.57  5952.5 1598.27  5970.1 1597.48  5983.5 1599.12
  6013.7 1608.17  6047.2 1621.14    6064 1625.91    6093 1630.49  6144.5 1634.44
  6252.5 1637.86  6279.3 1640.04  6280.9 1668.87  6287.6 1640.57  6337.5  1645.2
#Mann= 9 ,-1 , 0
  4795.8     .07       0  4998.9     .05       0    5016     .07       0
  5030.8    .035       0  5165.9    .045       0  5562.5     .07       0
  5755.5    .035       0  5952.5     .07       0    6093      .1       0
Bank Sta=4998.9,5016
XS Rating Curve= 0 ,0
Exp/Cntr=0.3,0.1

Type RM Length L Ch R = 1 ,10491   ,444,444,444
BEGIN DESCRIPTION:
Stream0040 16.0
END DESCRIPTION:
XS GIS Cut Line= 3
       1969480.5     13916628.96        1969475.       13916175.
        1968575.       13914975.
#Sta/Elev= 30
  4550.6 1608.24  4601.8 1603.22    4817 1596.69    4859 1587.86    4913 1583.68
    4967 1581.73    4976 1578.88  4976.4 1574.65  4976.9 1574.15  4993.6 1574.65
    4994 1580.18  5004.6 1581.74  5052.8 1583.35    5129 1585.34  5285.1 1585.79
  5585.6 1586.47  5717.3 1589.29  5774.2 1593.79  5829.6 1594.89    5847 1595.67
  5996.4 1605.61  6039.9 1610.04  6057.4 1610.14  6164.4 1619.97  6247.9 1627.47
  6360.1 1633.47  6371.4 1635.22  6397.6 1644.81  6442.6 1656.67  6504.6 1661.43
#Mann= 11 ,-1 , 0
  4550.6     .07       0  4976.4     .05       0  4993.6     .07       0
  5052.8    .035       0    5129     .07       0  5285.1    .045       0
  5717.3     .07       0  5829.6    .035       0    5847     .07       0
  6057.4      .1       0  6164.4     .07       0
Bank Sta=4976.4,4993.6
XS Rating Curve= 0 ,0
Exp/Cntr=0.3,0.1

Type RM Length L Ch R = 1 ,10047   ,208,208,208
BEGIN DESCRIPTION:
Stream0040 15.0
END DESCRIPTION:
XS GIS Cut Line= 4
      1969525.02     13916624.98      1969869.28     13916362.96
      1969874.97     13916258.96        1969175.       13915225.
#Sta/Elev= 30
  4529.8 1606.55  4535.9    1606  4592.6 1602.59  4636.1 1595.13  4656.7 1593.27
  4732.1 1590.94  4833.3 1585.38  4886.7 1583.68  4962.1 1583.45  4971.8 1582.21
  4983.8  1582.2  5004.9 1578.38  5005.3  1572.9  5005.8  1572.4  5022.5  1572.9
  5022.9 1577.81  5037.9  1580.6    5065 1580.11  5082.6 1581.91  5162.9 1581.69
  5501.7 1582.63  5885.9 1583.77  6064.9  1584.2  6117.5 1584.87  6167.1 1587.43
  6179.9 1587.17  6234.8 1589.55  6275.2  1595.3  6283.8 1594.86  6315.2 1596.15
#Mann= 10 ,-1 , 0
  4529.8    .035       0  4535.9     .07       0  4833.3     .07       0
  5005.3     .05       0  5022.5     .07       0  5162.9     .07       0
  5501.7    .045       0  5885.9    .035       0  6064.9    .045       0
  6179.9     .07       0
Bank Sta=5005.3,5022.5
XS Rating Curve= 0 ,0
Exp/Cntr=0.3,0.1

Type RM Length L Ch R = 1 ,9839    ,279,279,279
BEGIN DESCRIPTION:
Mapping XS 652689fe
END DESCRIPTION:
XS GIS Cut Line= 3
      1970485.82     13916701.81       1970121.2      13916380.6
      1969175.02     13915126.27
#Sta/Elev= 30
  4444.6 1614.31  4654.3 1607.64  4726.8 1600.77  4756.4 1598.09  4794.6 1584.83
  4817.1 1580.78  4886.1 1580.65  4954.2 1580.77  4964.4 1577.21  4970.3 1571.42
  4970.8 1570.92  4988.5 1571.42  4990.6 1575.56  4997.1 1578.96  5007.8 1580.68
    5194 1581.42  5236.5 1581.28  5313.3 1581.03  5439.5 1581.63  5550.7 1582.03
  5563.2 1582.37  5719.2 1582.35  5798.4  1582.5  6018.3  1583.2    6140 1583.59
  6267.9 1584.96  6418.6 1594.88  6445.1 1601.65  6472.9 1613.88  6501.7 1620.75
#Mann= 16 ,-1 , 0
  4444.6     .07       0  4726.8      .1       0  4886.1     .07       0
  4970.3     .05       0  4988.5     .07       0    5194    .045       0
  5236.5    .035       0  5313.3     .07       0  5439.5    .045       0
  5550.7     .07       0  5563.2    .045       0  5719.2    .035       0
  5798.4    .045       0  6018.3    .035       0    6140    .045       0
  6267.9     .07       0
Bank Sta=4970.3,4988.5
XS Rating Curve= 0 ,0
Exp/Cntr=0.3,0.1

Type RM Length L Ch R = 1 ,9560    ,869,869,869
BEGIN DESCRIPTION:
Stream0040 14.0
END DESCRIPTION:
XS GIS Cut Line= 3
        1970375.     13916424.98        1970325.       13916225.
      1969124.99     13915024.99
#Sta/Elev= 30
  4794.4 1606.73  4920.6 1601.63  4951.4  1585.3  4969.5 1569.86    4970 1569.36
  4987.8 1569.86  4991.7 1576.01  4998.4 1578.24  5014.3 1578.52    5092 1579.96
  5183.3 1577.68  5200.2 1581.31  5216.9 1577.72  5318.7  1578.1  5418.7 1581.91
  5630.4 1581.19  5830.4 1581.32  5935.3 1581.52  6127.3 1582.75  6177.5 1583.16
  6327.7 1584.38  6445.4 1589.72  6479.4    1595  6498.2 1595.18  6504.8  1598.4
  6545.4  1607.3  6562.4 1614.67  6617.3 1624.99    6630 1629.93  6697.6 1645.51
#Mann= 10 ,-1 , 0
  4794.4     .07       0  4969.5     .05       0  4987.8     .07       0
  5014.3     .07       0  5630.4    .045       0  5830.4    .035       0
  5935.3    .045       0  6127.3    .035       0  6177.5    .045       0
  6327.7     .07       0
Bank Sta=4969.5,4987.8
XS Rating Curve= 0 ,0
Exp/Cntr=0.3,0.1

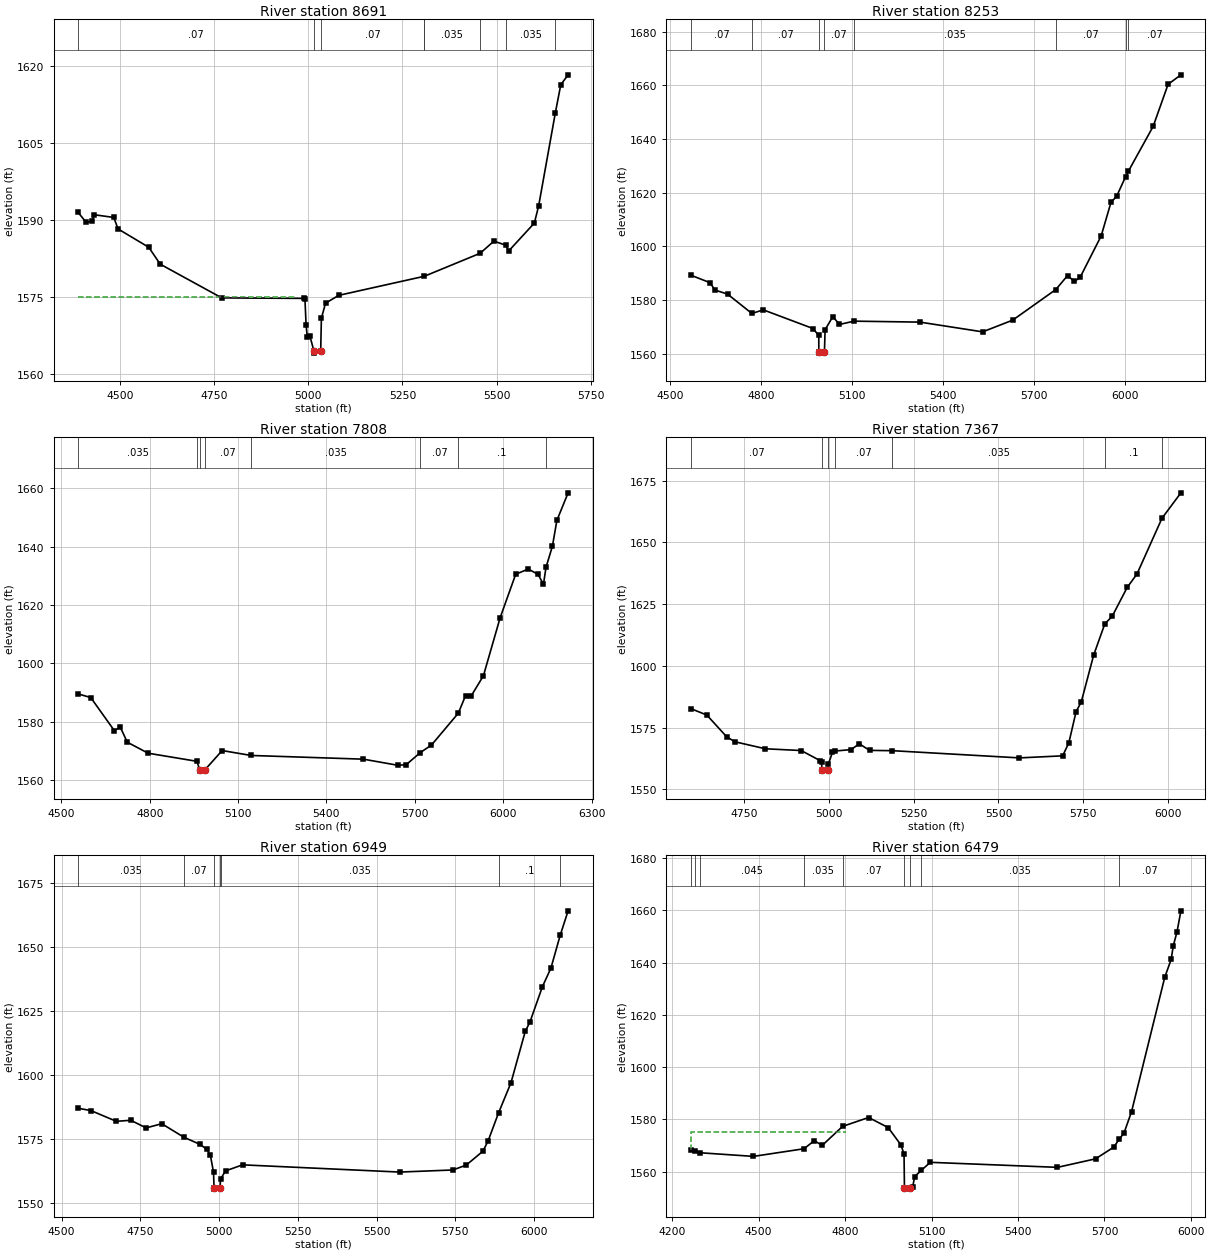
Type RM Length L Ch R = 1 ,8691    ,438,438,438
BEGIN DESCRIPTION:
Stream0040 13.0
END DESCRIPTION:
XS GIS Cut Line= 3
      1970658.19     13916176.83        1970575.       13915575.
      1970224.99     13914974.98
#Sta/Elev= 30
    4388 1591.53  4409.4 1589.58  4425.6 1589.77  4430.6 1591.06    4483 1590.53
  4494.2  1588.3    4576 1584.72  4606.3 1581.44  4769.8 1574.88  4989.7 1574.78
  4990.9 1574.66  4993.9  1569.7  4997.2 1567.23  5004.1 1567.47  5014.4 1564.63
  5014.9 1564.13  5032.8 1564.63  5034.6  1570.9  5045.6 1573.85  5080.7 1575.37
  5308.4 1579.09  5456.5 1583.56    5493 1585.92  5524.6 1585.13    5532 1583.98
  5600.5 1589.44  5611.9 1592.78  5656.4 1610.94  5670.7 1616.35  5690.2 1618.28
#Mann= 8 ,-1 , 0
    4388     .07       0  5014.4     .05       0  5032.8     .07       0
  5308.4    .045       0  5308.4    .035       0  5456.5     .07       0
  5524.6    .035       0  5656.4      .1       0
#XS Ineff= 2 , 0
         4964.67 1575.03 5079.49         1575.11
Permanent Ineff=
       F       F
Bank Sta=5014.4,5032.8
XS Rating Curve= 0 ,0
Exp/Cntr=0.3,0.1

Type RM Length L Ch R = 1 ,8253    ,445,445,445
BEGIN DESCRIPTION:
Stream0040 12.0
END DESCRIPTION:
XS GIS Cut Line= 3
      1970775.01     13916124.97        1970925.       13915725.
        1971212.     13914569.58
#Sta/Elev= 30
  4568.2 1589.21  4631.6 1586.42  4647.6 1583.68  4689.3 1582.17  4769.6 1574.95
  4807.4 1576.29  4971.2 1569.34  4990.5 1566.74  4990.7 1560.66  4991.2 1560.16
  5009.2 1560.66  5011.4 1568.89    5037  1573.8  5058.6 1570.84    5107 1572.08
  5324.5 1571.72  5531.4 1568.09  5630.7 1572.46  5773.1 1583.88  5811.6 1589.05
  5834.5 1586.89  5853.1 1588.39  5922.7 1603.87  5955.1 1616.39  5973.6  1618.6
  6003.5 1625.98  6012.1 1627.89  6094.2 1644.67  6143.6 1660.38  6185.9 1663.91
#Mann= 8 ,-1 , 0
  4568.2     .07       0  4769.6     .07       0  4990.7     .05       0
  5009.2     .07       0    5107    .035       0  5773.1     .07       0
  6003.5      .1       0  6012.1     .07       0
#XS Ineff= 2 , 0
                         5044.73         1571.72
Permanent Ineff=
       F       F
Bank Sta=4990.7,5009.2
XS Rating Curve= 0 ,0
Exp/Cntr=0.3,0.1

Type RM Length L Ch R = 1 ,7808    ,441,441,441
BEGIN DESCRIPTION:
Stream0040 11.0
END DESCRIPTION:
XS GIS Cut Line= 3
      1971124.98     13916275.03        1971325.       13915875.
        1971525.       13914675.
#Sta/Elev= 30
  4556.7 1589.57  4599.7 1588.34  4679.7 1577.03  4700.3 1578.16  4723.8 1573.05
  4794.7 1569.28  4960.6  1566.5  4969.4 1563.65  4969.9 1563.15  4987.9 1563.65
    5046 1570.19  5144.2 1568.51  5525.5 1567.24  5644.1 1565.12  5671.4  1565.4
  5718.7  1569.5  5756.6 1572.07  5847.8 1582.99  5872.2 1588.96  5890.4  1588.7
    5933 1595.79  5989.7 1615.63  6042.5  1630.5  6085.1  1632.3  6118.5 1630.46
  6136.8 1627.05  6145.4 1632.86  6167.2 1640.11  6182.4 1648.94  6220.5 1658.37
#Mann= 8 ,-1 , 0
  4556.7    .035       0  4960.6     .07       0  4969.4     .05       0
  4987.9     .07       0  5144.2    .035       0  5718.7     .07       0
  5847.8      .1       0  6145.4     .07       0
#XS Ineff= 2 , 0
                          5145.4         1567.83
Permanent Ineff=
       F       F
Bank Sta=4969.4,4987.9
XS Rating Curve= 0 ,0
Exp/Cntr=0.3,0.1

Type RM Length L Ch R = 1 ,7367    ,418,418,418
BEGIN DESCRIPTION:
Stream0040 10.0
END DESCRIPTION:
XS GIS Cut Line= 3
      1971324.99     13916325.01        1971675.       13916125.
      1971857.06     13915098.04
#Sta/Elev= 30
  4592.2 1582.66  4639.4 1580.06  4698.2 1571.21  4722.4 1569.23  4812.2  1566.4
  4917.9 1565.69  4974.6 1561.53  4978.1 1560.99  4978.8 1557.85  4979.3 1557.35
  4997.4 1557.85  4997.8 1560.16    5010 1564.93  5017.7  1565.5  5064.8 1566.05
  5089.2 1568.42  5119.6 1565.75  5187.1 1565.63  5561.6 1562.71  5689.4 1563.54
  5707.7 1568.87    5729 1581.45  5744.2 1585.34  5780.8 1604.32  5813.9 1617.04
  5835.2 1619.98  5879.7 1631.73  5908.8 1637.21  5982.4 1659.76  6038.3 1670.06
#Mann= 7 ,-1 , 0
  4592.2     .07       0  4978.8     .05       0  4997.4     .07       0
  5017.7     .07       0  5187.1    .035       0  5813.9      .1       0
  5982.4     .07       0
Bank Sta=4978.8,4997.4
XS Rating Curve= 0 ,0
Exp/Cntr=0.3,0.1

Type RM Length L Ch R = 1 ,6949    ,470,470,470
BEGIN DESCRIPTION:
Stream0040 9.0
END DESCRIPTION:
XS GIS Cut Line= 4
      1971891.32     13916648.23      1972033.32     13916318.63
        1972025.       13916225.      1971893.33     13915129.47
#Sta/Elev= 30
    4552  1586.9  4593.3 1585.96  4673.6 1581.78  4719.3 1582.19  4768.3 1579.21
  4817.8 1580.85  4888.8 1575.52    4939 1572.81  4960.1 1570.95  4972.2 1568.59
  4982.2 1561.89  4983.9 1555.81  4984.4 1555.31  5002.5 1555.81    5005 1559.34
  5020.4 1562.43  5074.5 1564.79  5573.4 1561.97  5742.6 1562.79  5784.9 1564.71
  5837.8 1570.11  5854.4 1574.19  5887.6 1585.14  5926.8 1596.82  5972.2 1616.89
  5987.3 1620.63  6026.6 1634.32  6053.8 1641.63    6083 1654.36  6108.3 1663.96
#Mann= 7 ,-1 , 0
    4552    .035       0  4888.8     .07       0  4983.9     .05       0
  5002.5     .07       0    5005    .035       0  5887.6      .1       0
    6083     .07       0
Bank Sta=4983.9,5002.5
XS Rating Curve= 0 ,0
Exp/Cntr=0.3,0.1

Type RM Length L Ch R = 1 ,6479    ,469,469,469
BEGIN DESCRIPTION:
Stream0040 8.0
END DESCRIPTION:
XS GIS Cut Line= 4
      1972894.23     13916489.77        1972375.       13915975.
       1972296.6     13915889.48      1971945.41     13915111.44
#Sta/Elev= 30
  4264.6 1568.41  4279.9 1567.95  4295.1 1567.28  4481.8 1565.88  4657.3  1568.8
    4693 1571.89  4720.3 1570.07  4791.3 1577.36  4881.5 1580.75  4949.4 1576.91
  4993.9 1570.23  5004.5 1566.74  5005.9 1553.86  5006.4 1553.36  5024.8 1553.86
  5034.3 1554.17  5041.6 1558.18  5064.9  1560.6  5095.8 1563.61    5537 1561.69
    5669 1564.94  5731.5 1569.35    5752  1572.5  5768.3 1574.93  5794.1    1583
  5909.3 1634.38  5931.6 1641.23  5938.9 1646.41  5951.8 1651.71  5965.4 1659.79
#Mann= 9 ,-1 , 0
  4264.6    .045       0  4279.9     .07       0  4295.1    .045       0
  4657.3    .035       0  4791.3     .07       0  5005.9     .05       0
  5024.8     .07       0  5064.9    .035       0    5752     .07       0
#XS Ineff= 2 , 0
         4801.35 1575.28
Permanent Ineff=
       F       F
Bank Sta=5005.9,5024.8
XS Rating Curve= 0 ,0
Exp/Cntr=0.3,0.1

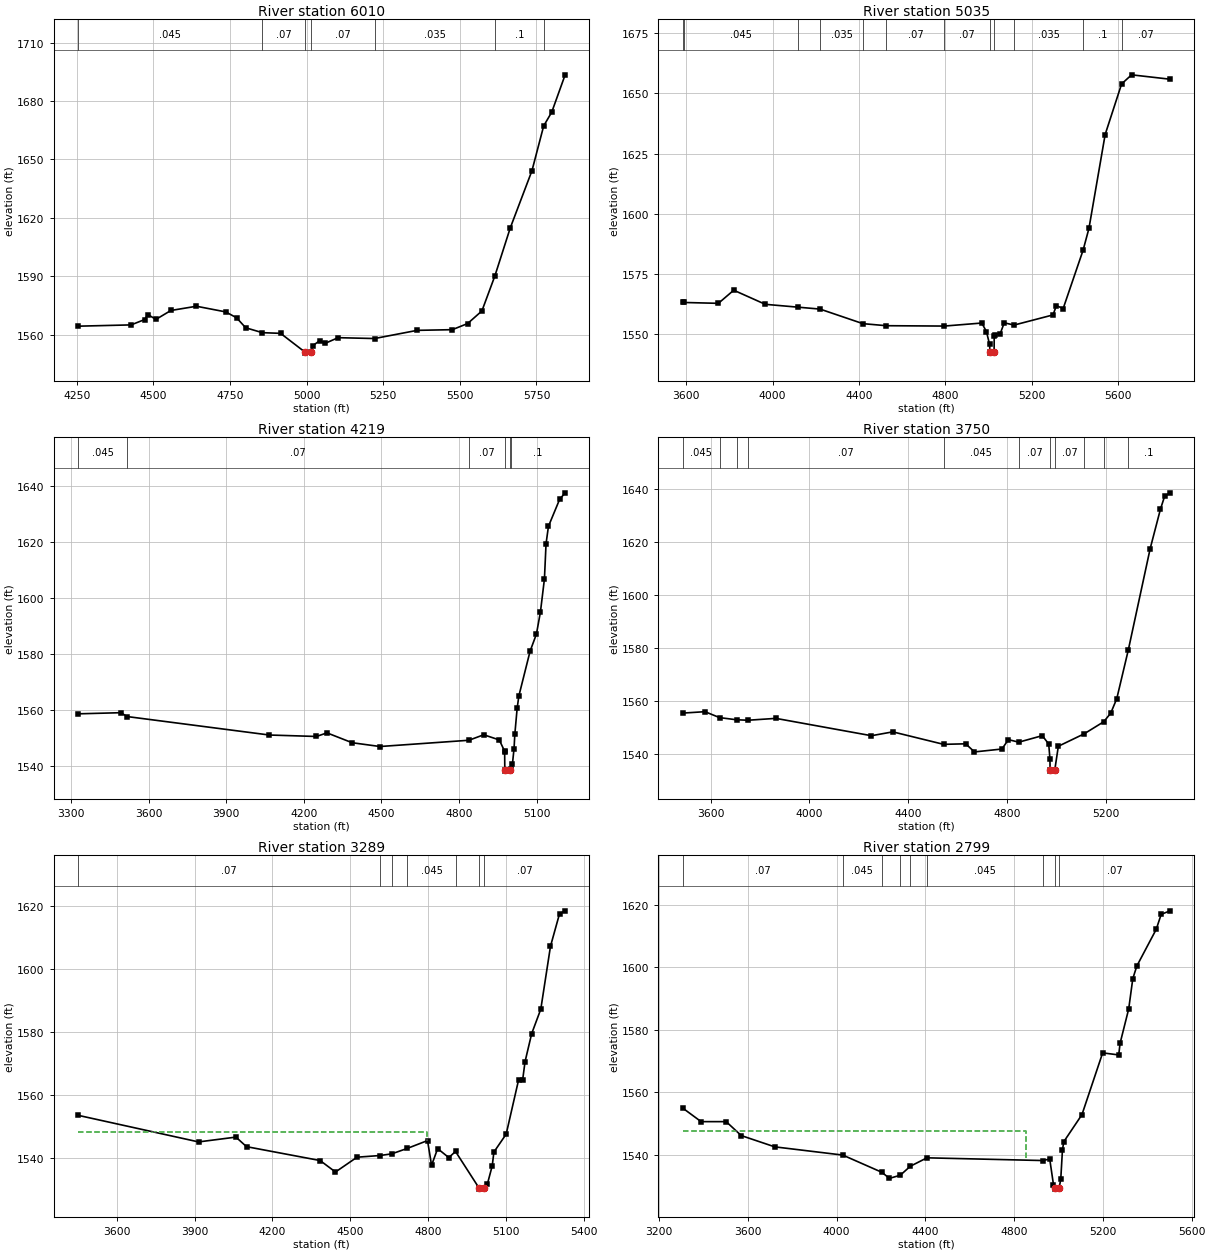
Type RM Length L Ch R = 1 ,6010    ,975,975,975
BEGIN DESCRIPTION:
Stream0040 7.0
END DESCRIPTION:
XS GIS Cut Line= 3
      1972861.75     13916258.25        1972575.       13915575.
      1971975.01     13914975.01
#Sta/Elev= 30
    4254 1564.42  4427.7 1565.08  4471.3 1567.81  4482.7 1570.37  4508.5 1567.89
  4557.3 1572.48  4640.8 1574.65  4736.2 1571.75  4771.5 1568.75  4801.4  1563.6
  4855.8 1561.09  4915.2 1560.74    4995 1551.09  4995.5 1550.59    5014 1551.09
  5020.4 1554.45  5042.6 1556.95  5059.6 1555.55    5103 1558.52  5221.7 1558.08
  5360.8 1562.28  5475.4 1562.63  5525.3 1565.76    5572 1572.25  5614.2 1590.17
  5664.2 1614.73  5735.2 1644.19  5773.5  1667.2    5800 1674.35  5843.5 1693.43
#Mann= 7 ,-1 , 0
    4254    .045       0  4855.8     .07       0    4995     .05       0
    5014     .07       0  5221.7    .035       0  5614.2      .1       0
  5773.5     .07       0
Bank Sta=4995,5014
XS Rating Curve= 0 ,0
Exp/Cntr=0.3,0.1

Type RM Length L Ch R = 1 ,5035    ,816,816,816
BEGIN DESCRIPTION:
Stream0040 6.1
END DESCRIPTION:
XS GIS Cut Line= 3
      1972953.01     13916211.05      1973171.22     13914985.38
      1972872.41      13914017.4
#Sta/Elev= 30
  3583.7 1563.17  3587.9 1563.16  3748.6  1562.8  3819.8 1568.25  3966.1 1562.39
  4119.9 1561.19  4219.8 1560.41  4418.5 1554.36    4527 1553.51  4795.9 1553.36
  4969.4 1554.62    4991 1551.05  5005.4 1545.76  5007.3 1542.62  5007.8 1542.12
  5026.4 1542.62    5027  1549.2  5029.4  1549.8  5054.5 1550.13  5073.3 1554.71
  5119.2 1553.78  5299.4 1557.99  5315.1 1561.83  5346.5 1560.64    5439 1584.92
    5466 1593.94  5541.1 1632.92  5617.3 1653.93  5663.6 1657.71  5841.7 1655.89
#Mann= 12 ,-1 , 0
  3583.7     .07       0  3587.9    .045       0  4119.9     .07       0
  4219.8    .035       0  4418.5    .045       0    4527     .07       0
  4795.9     .07       0  5007.3     .05       0  5026.4     .07       0
  5119.2    .035       0    5439      .1       0  5617.3     .07       0
Bank Sta=5007.3,5026.4
XS Rating Curve= 0 ,0
Exp/Cntr=0.3,0.1

Type RM Length L Ch R = 1 ,4219    ,469,469,469
BEGIN DESCRIPTION:
Stream0040 6.0
END DESCRIPTION:
XS GIS Cut Line= 3
      1973112.08     13916118.47        1973875.       13914625.
        1973925.     13914425.01
#Sta/Elev= 30
  3326.8 1558.53  3493.1 1558.94  3516.6 1557.56  4066.7 1550.94  4248.6 1550.42
  4289.5 1551.71  4386.7 1548.18  4494.3 1546.82    4838 1549.06  4895.4 1551.03
  4955.5 1549.18  4975.9 1545.17  4976.2 1544.96  4976.8  1538.5  4977.3    1538
  4995.9  1538.5  5001.9 1538.84  5006.3 1540.57  5012.5 1546.05  5015.6 1551.28
  5024.5 1560.51  5031.1 1564.93  5074.4 1580.94  5099.1 1587.13  5114.6 1595.09
    5130  1606.9  5136.2 1619.48  5145.5 1625.73  5188.8 1635.41    5210 1637.73
#Mann= 6 ,-1 , 0
  3326.8    .045       0  3516.6     .07       0    4838     .07       0
  4976.8     .05       0  4995.9     .07       0  5001.9      .1       0
Bank Sta=4976.8,4995.9
XS Rating Curve= 0 ,0
Exp/Cntr=0.3,0.1

Type RM Length L Ch R = 1 ,3750    ,461,461,461
BEGIN DESCRIPTION:
Stream0040 5.0
END DESCRIPTION:
XS GIS Cut Line= 3
      1973333.88     13916147.25        1974225.       13914925.
        1974325.     13914474.99
#Sta/Elev= 30
  3487.4 1555.56  3577.3 1556.09  3636.4 1553.86  3705.3 1553.04  3751.5 1552.87
  3864.4 1553.57  4251.5 1547.04    4338 1548.49  4543.9 1543.79  4633.4 1543.99
  4668.8 1540.93  4780.2 1542.03  4806.2 1545.56  4848.5 1544.61  4943.6 1547.06
  4969.6 1543.92  4974.6 1538.35  4975.2  1534.2  4975.7  1533.7  4994.3  1534.2
  5008.6 1543.07  5113.2 1547.75  5192.2 1552.28  5220.7 1555.51  5245.3 1560.99
  5292.2  1579.4  5380.5 1617.48    5422  1632.3  5438.9 1637.16    5461 1638.53
#Mann= 11 ,-1 , 0
  3487.4    .045       0  3636.4     .07       0  3705.3    .045       0
  3751.5     .07       0  4543.9    .045       0  4848.5     .07       0
  4975.2     .05       0  4994.3     .07       0  5113.2      .1       0
  5192.2     .07       0  5292.2      .1       0
Bank Sta=4975.2,4994.3
XS Rating Curve= 0 ,0
Exp/Cntr=0.3,0.1

Type RM Length L Ch R = 1 ,3289    ,490,490,490
BEGIN DESCRIPTION:
Stream0040 4.0
END DESCRIPTION:
XS GIS Cut Line= 3
      1973625.01     13916224.99        1974625.       13915025.
      1974725.01     13914724.96
#Sta/Elev= 30
  3450.5  1553.6  3915.7 1545.13  4059.7 1546.66  4100.5 1543.62  4384.3 1539.21
  4443.4 1535.56  4526.5 1540.27  4614.4  1540.8  4660.1 1541.33  4720.8 1543.08
  4798.3 1545.56  4813.9 1537.69  4837.3    1543  4880.3 1540.15  4906.2 1542.09
  4995.7 1530.62  4996.2 1530.12  5014.8 1530.62  5028.8 1531.66  5047.8 1537.55
  5054.1  1541.9  5101.5  1547.6  5149.6 1564.94  5164.8 1564.72  5174.2 1570.63
  5199.7 1579.53    5235 1587.35  5272.3 1607.32  5307.1 1617.65  5328.8  1618.6
#Mann= 7 ,-1 , 0
  3450.5     .07       0  4614.4    .045       0  4660.1     .07       0
  4720.8    .045       0  4906.2     .07       0  4995.7     .05       0
  5014.8     .07       0
#XS Ineff= 2 , 0
         4795.44 1548.21
Permanent Ineff=
       F       F
Bank Sta=4995.7,5014.8
XS Rating Curve= 0 ,0
Exp/Cntr=0.3,0.1

Type RM Length L Ch R = 1 ,2799    ,728,728,728
BEGIN DESCRIPTION:
Stream0040 3.0
END DESCRIPTION:
XS GIS Cut Line= 3
      1973874.99     13916325.01        1975075.       13915125.
       1975130.4     13914629.96
#Sta/Elev= 30
  3307.3 1554.95  3389.9 1550.63  3502.8 1550.63  3570.7 1546.17  3721.7 1542.56
    4028 1539.93  4204.2 1534.42  4238.4 1532.47  4287.2 1533.48  4332.4 1536.35
  4407.4 1539.05  4928.4 1538.18  4960.5 1538.66  4977.5 1530.42  4984.1 1529.53
  4984.6 1529.03  5003.2 1529.53  5010.2 1532.17  5017.9  1541.6  5023.9 1544.21
  5105.7 1552.87    5199 1572.64  5271.4 1571.98  5277.5  1575.7  5316.4 1586.73
  5334.8 1596.39  5352.9 1600.43  5440.5  1612.2  5462.6 1616.97  5502.5  1618.1
#Mann= 9 ,-1 , 0
  3307.3     .07       0    4028    .045       0  4204.2     .07       0
  4287.2    .045       0  4332.4     .07       0  4407.4    .045       0
  4928.4     .07       0  4984.1     .05       0  5003.2     .07       0
#XS Ineff= 2 , 0
         4854.17 1547.77
Permanent Ineff=
       F       F
Bank Sta=4984.1,5003.2
XS Rating Curve= 0 ,0
Exp/Cntr=0.3,0.1