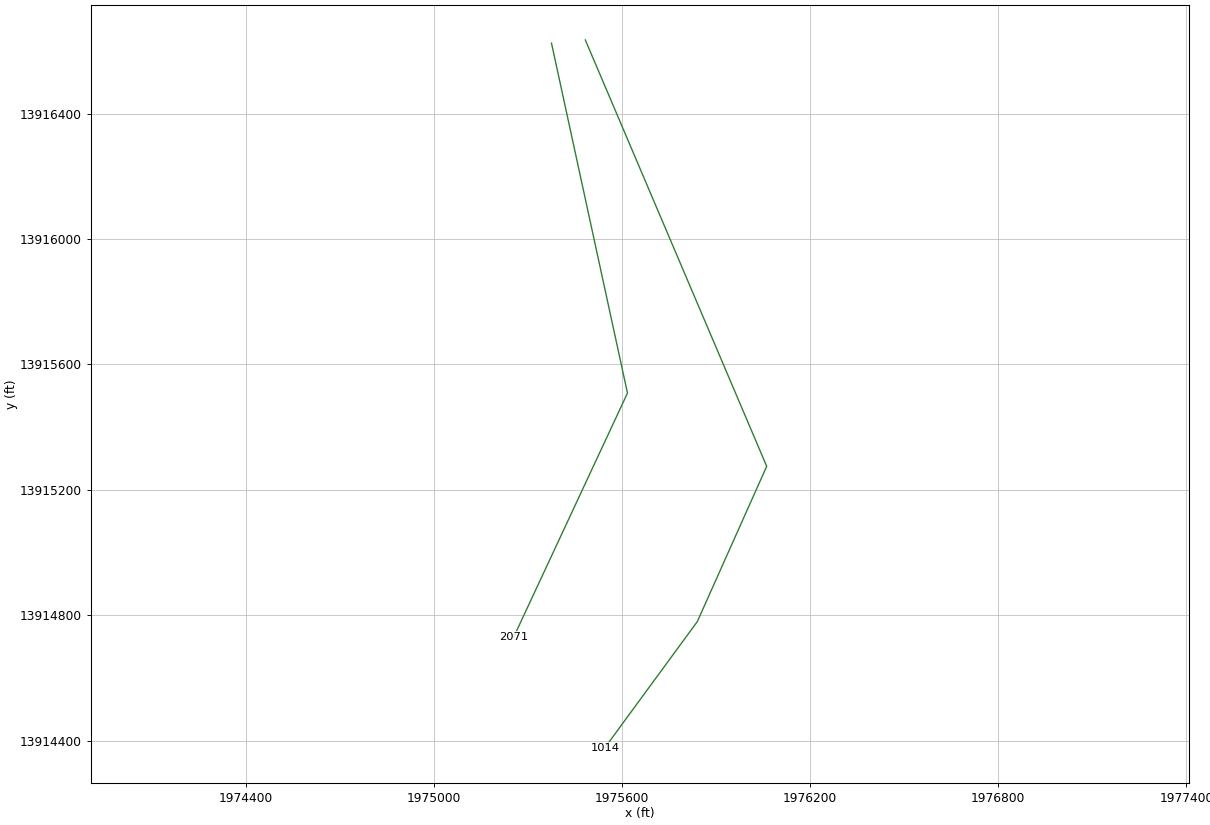
HEC-RAS study Stream0040.prj: Stream0040 Base Level Engineering

--- Stream0040.g01 (geometry) --- (continued)

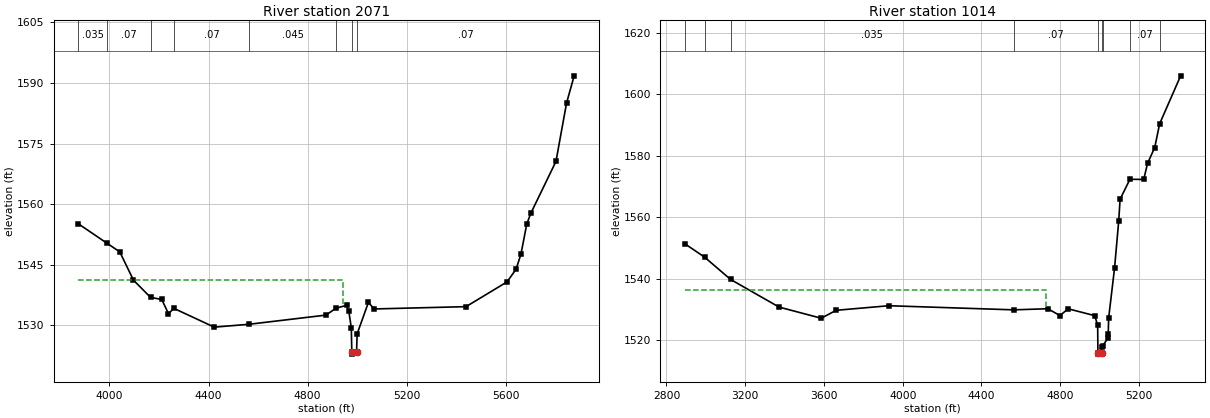
Type RM Length L Ch R = 1 ,2071    ,1057,1057,1057
BEGIN DESCRIPTION:
Stream0040 2.0
END DESCRIPTION:
XS GIS Cut Line= 3
      1975374.99     13916625.02       1975617.4     13915508.83
      1975254.81     13914731.22
#Sta/Elev= 30
  3874.8 1555.16  3990.3 1550.35    4042 1548.21  4097.3  1541.2  4166.1 1536.95
  4211.3 1536.43  4238.5 1532.91    4260 1534.23  4423.1 1529.58  4563.5 1530.29
    4874 1532.56  4914.8  1534.3  4956.9 1534.96  4966.1 1533.48    4976 1529.37
    4978  1523.4  4978.5  1522.9  4997.1  1523.4  4999.5  1527.9  5044.9 1535.69
  5068.4 1534.08  5438.8 1534.65  5604.3 1540.78  5640.7 1543.93  5660.5 1547.68
  5683.7 1555.08    5700 1557.74  5801.6  1570.6  5844.5 1585.09    5875 1591.78
#Mann= 8 ,-1 , 0
  3874.8    .035       0  3990.3     .07       0  4166.1    .035       0
    4260     .07       0  4563.5    .045       0  4914.8     .07       0
    4978     .05       0  4997.1     .07       0
#XS Ineff= 2 , 0
         4940.58 1541.21
Permanent Ineff=
       F       F
Bank Sta=4978,4997.1
XS Rating Curve= 0 ,0
Exp/Cntr=0.3,0.1

Type RM Length L Ch R = 1 ,1014    ,0,0,0
BEGIN DESCRIPTION:
Stream0040 1.0
END DESCRIPTION:
XS GIS Cut Line= 4
       1975482.9     13916635.17       1976061.5     13915275.14
      1975840.18     13914779.95       1975545.6     13914378.03
#Sta/Elev= 30
    2893 1551.34  2993.3 1546.99  3125.6 1539.72  3371.8 1530.73  3586.1  1527.1
  3661.9 1529.68  3929.3 1531.17  4563.8 1529.83  4737.4 1530.19  4798.6 1527.97
  4840.4 1530.17  4975.3 1527.94  4990.3  1524.8  4991.5 1515.92    4992 1515.42
  5010.7 1515.92  5011.8  1517.9  5016.9 1518.21  5041.5 1520.54    5044  1522.1
  5046.1 1527.18  5076.2  1543.5  5097.3  1558.8  5104.1  1565.8  5154.2 1572.32
  5224.3 1572.26  5243.6 1577.48  5280.1 1582.65  5305.1 1590.37  5411.7 1605.98
#Mann= 9 ,-1 , 0
    2893    .035       0  2993.3     .07       0  3125.6    .035       0
  4563.8     .07       0  4991.5     .05       0  5010.7     .07       0
  5016.9    .035       0  5154.2     .07       0  5305.1      .1       0
#XS Ineff= 2 , 0
         4728.48 1536.32
Permanent Ineff=
       F       F
Bank Sta=4991.5,5010.7
XS Rating Curve= 0 ,0
Exp/Cntr=0.3,0.1

Chan Stop Cuts=-1
Use User Specified Reach Order=0
Composite Channel Slope=5