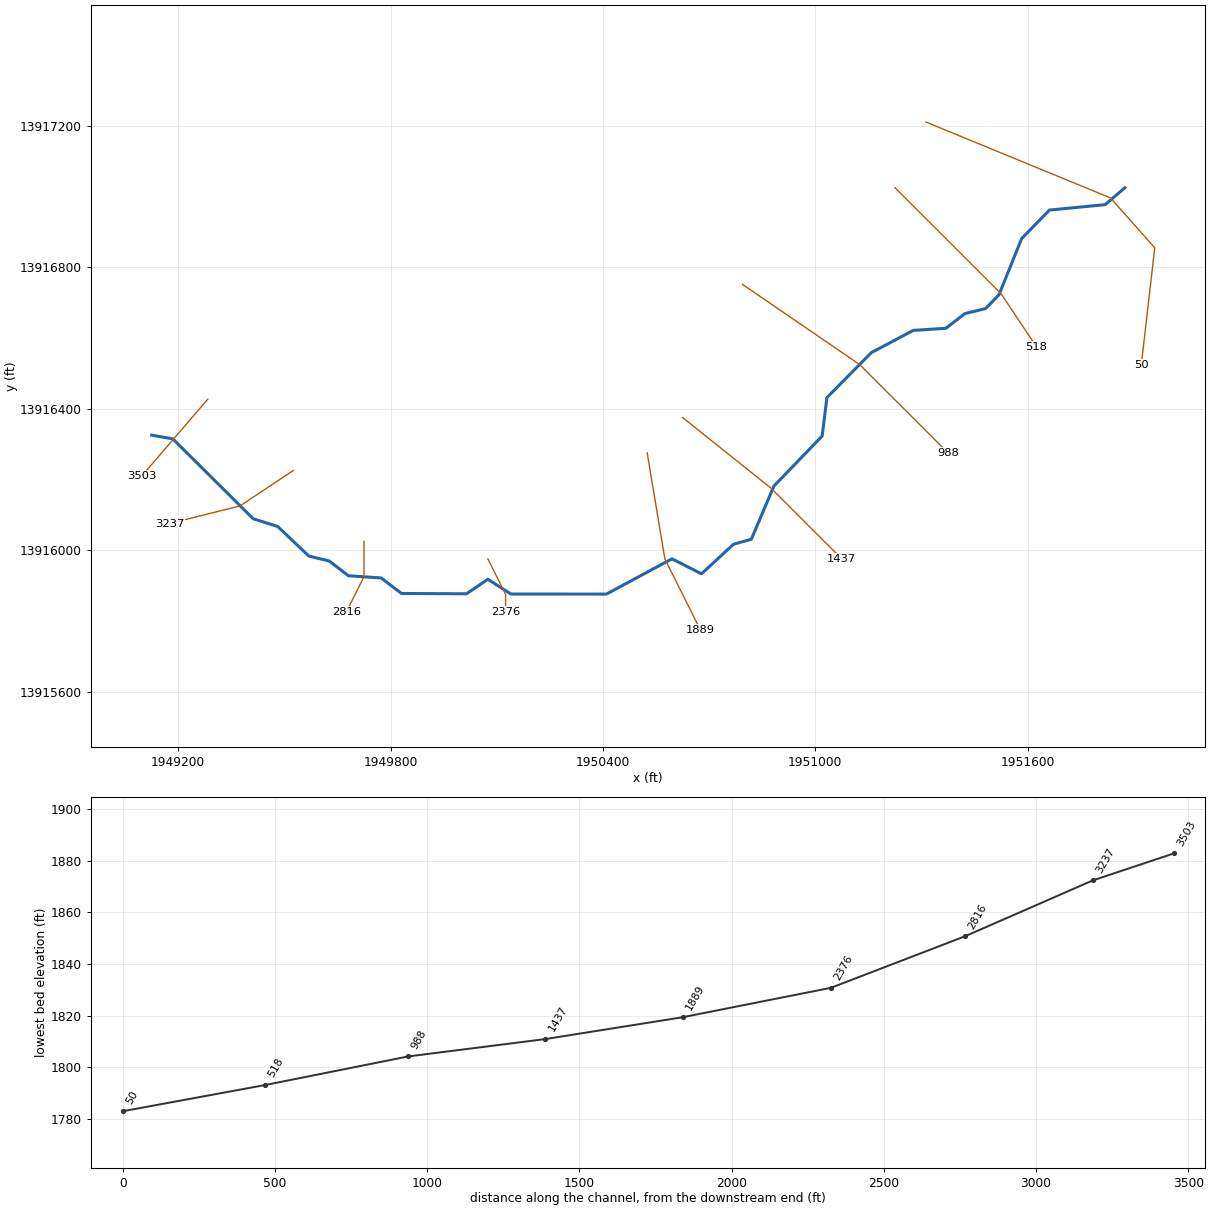
--- Stream0041.prj (project) ---

Proj Title=Stream0041 Base Level Engineering
Current Plan=p01
Default Exp/Contr=0.3,0.1
English Units
Geom File=g01
Flow File=f01
Plan File=p01
Y Axis Title=Elevation
X Axis Title(PF)=Main Channel Distance
X Axis Title(XS)=Station
BEGIN DESCRIPTION:
Stream0041
END DESCRIPTION:
DSS Export Rating Curves= 0
DSS Export Rating Curve Sorted= 0
DSS Export Volume Flow Curves= 0
DXF OffsetX= 0
DXF OffsetY= 0
DXF ScaleX= 1
DXF ScaleY= 10

--- Stream0041.p01 (plan) ---

Plan Title=Multiple Run
Short Identifier=Multiple
Geom File=g01
Flow File=f01
Subcritical Flow
K Sum by GR= 0
Std Step Tol= 0.01
Critical Tol= 0.01
Num of Std Step Trials= 20
Max Error Tol= 0.3
Flow Tol Ratio= 0.001
Split Flow NTrial= 30
Split Flow Tol= 0.02
Split Flow Ratio= 0.02
Log Output Level= 0
Friction Slope Method= 1
Unsteady Friction Slope Method= 2
Unsteady Bridges Friction Slope Method= 1
Parabolic Critical Depth
Global Vel Dist=  1 , 1 , 1
Global Log Level= 0
CheckData=True
Encroach Param= -1, 0, 0, 0
BEGIN DESCRIPTION:
Multiple Run
END DESCRIPTION:

--- Stream0041.f01 (steady flow) ---

Flow Title=Multiple
Number of Profiles=7
Profile Names=10-year,25-year,50-year,1pct_min,100-year,1pct_plu,500-year
River Rch & RM= Stream0041,Reach-1,3503
     304     473     621     398     793    1583    1269
River Rch & RM= Stream0041,Reach-1,2816
     655    1077    1468     971    1937    3864    3317
Boundary for River Rch & Prof#=Stream0041,Reach-1,1
Up Type=0
Dn Type=3
Dn Slope=0.005
Boundary for River Rch & Prof#=Stream0041,Reach-1,2
Up Type=0
Dn Type=3
Dn Slope=0.005
Boundary for River Rch & Prof#=Stream0041,Reach-1,3
Up Type=0
Dn Type=3
Dn Slope=0.005
Boundary for River Rch & Prof#=Stream0041,Reach-1,4
Up Type=0
Dn Type=3
Dn Slope=0.005
Boundary for River Rch & Prof#=Stream0041,Reach-1,5
Up Type=0
Dn Type=3
Dn Slope=0.005
Boundary for River Rch & Prof#=Stream0041,Reach-1,6
Up Type=0
Dn Type=3
Dn Slope=0.005
Boundary for River Rch & Prof#=Stream0041,Reach-1,7
Up Type=0
Dn Type=3
Dn Slope=0.005

--- Stream0041.g01 (geometry) ---

Geom Title=Existing Conditions
Program Version=4.10

River Reach=Stream0041      ,Reach-1
Reach XY= 30
        1949125.       13916325.      1949184.79     13916314.49
      1949411.79     13916088.63      1949481.04     13916066.82
      1949568.95     13915983.16      1949627.17     13915968.86
      1949680.97     13915927.33       1949773.4     13915921.14
      1949830.94     13915877.26      1950014.56     13915876.38
        1950075.     13915917.44      1950140.16     13915875.66
      1950409.79     13915875.51       1950595.2     13915975.22
       1950678.4     13915932.83      1950769.25     13916016.68
      1950819.41     13916030.61      1950883.14     13916181.05
      1951019.48     13916322.57      1951032.86     13916431.17
      1951158.32     13916558.36      1951276.58     13916621.17
      1951369.04     13916627.33      1951422.85     13916668.85
      1951481.34     13916683.02      1951519.27     13916722.45
      1951583.13     13916881.07      1951661.66     13916961.64
      1951819.21     13916976.91        1951875.       13917025.

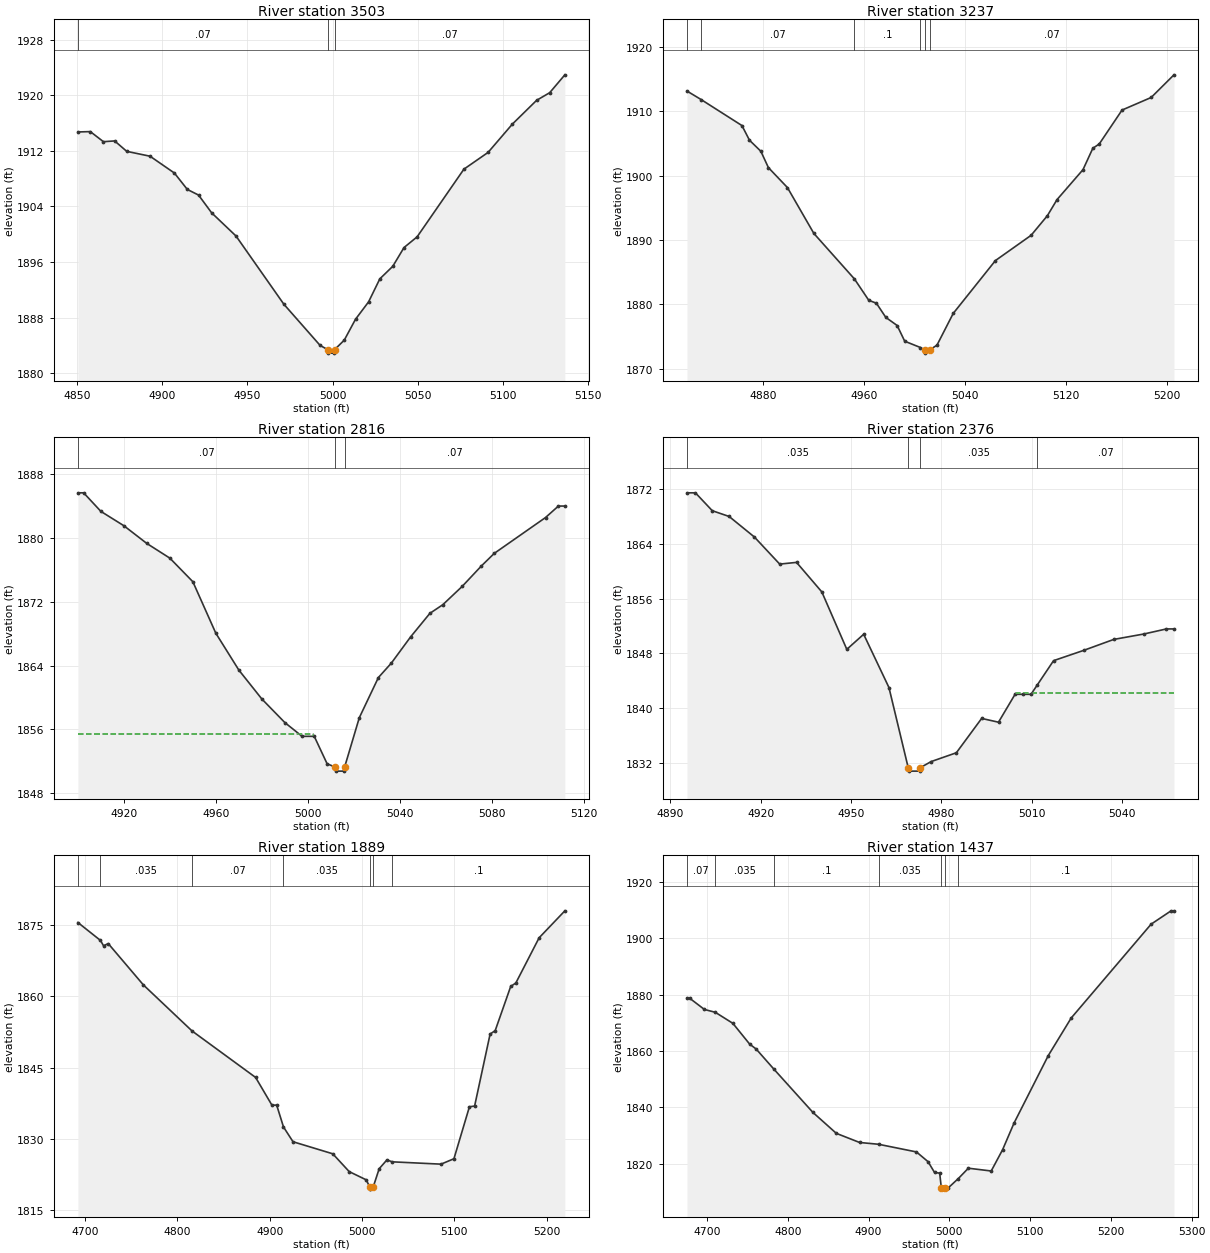
Type RM Length L Ch R = 1 ,3503    ,266,266,266
BEGIN DESCRIPTION:
Stream0041 8.0
END DESCRIPTION:
XS GIS Cut Line= 2
      1949283.71     13916426.74      1949097.16     13916209.83
#Sta/Elev= 30
  4850.4  1914.7  4857.7 1914.75  4865.4  1913.3    4872 1913.41  4879.1 1911.91
  4892.8 1911.21  4907.1 1908.79  4914.7 1906.43  4921.3 1905.62    4929 1903.06
  4943.3 1899.73  4971.4 1889.92  4992.7 1883.99  4997.2 1883.38  4997.5 1882.88
    5001 1882.88  5001.2 1883.38  5006.9 1884.75  5013.5 1887.75  5021.2 1890.26
  5027.8 1893.57  5035.4 1895.37    5042 1898.07  5049.7 1899.61  5077.2 1909.35
  5091.4 1911.76  5105.7 1915.84  5119.9 1919.25  5127.6 1920.35  5136.5 1922.92
#Mann= 3 ,-1 , 0
  4850.4     .07       0  4997.2     .05       0  5001.2     .07       0
Bank Sta=4997.2,5001.2
XS Rating Curve= 0 ,0
Exp/Cntr=0.3,0.1

Type RM Length L Ch R = 1 ,3237    ,421,421,421
BEGIN DESCRIPTION:
Stream0041 7.0
END DESCRIPTION:
XS GIS Cut Line= 3
      1949525.04     13916225.03        1949375.       13916125.
      1949174.98       13916075.
#Sta/Elev= 30
  4819.4 1913.15  4830.6 1911.83    4863 1907.79    4869 1905.51    4878  1903.8
    4884 1901.26  4899.1 1898.16  4920.1 1891.03  4952.3 1883.96  4963.7 1880.64
  4969.7  1880.2  4977.2 1877.99  4986.2 1876.73  4992.2 1874.29  5004.7 1873.31
    5008 1872.94  5008.3 1872.44    5012 1872.94  5017.8 1873.68  5030.7 1878.61
  5064.2 1886.82  5092.5 1890.74  5105.4 1893.78  5113.1 1896.29  5133.7 1900.94
  5141.5 1904.26  5146.6 1904.93  5164.7  1910.2  5187.8 1912.15  5205.9 1915.67
#Mann= 6 ,-1 , 0
  4819.4      .1       0  4830.6     .07       0  4952.3      .1       0
  5004.7     .07       0    5008     .05       0    5012     .07       0
Bank Sta=5008,5012
XS Rating Curve= 0 ,0
Exp/Cntr=0.3,0.1

Type RM Length L Ch R = 1 ,2816    ,440,440,440
BEGIN DESCRIPTION:
Stream0041 6.0
END DESCRIPTION:
XS GIS Cut Line= 3
        1949725.       13916025.        1949725.       13915925.
        1949675.       13915825.
#Sta/Elev= 30
    4900 1885.68  4902.5 1885.68    4910 1883.35    4920 1881.55    4930 1879.32
    4940 1877.48    4950 1874.52    4960 1868.05    4970 1863.43    4980  1859.8
    4990 1856.84  4997.5 1855.11  5002.8 1855.11  5008.4 1851.66    5012 1851.24
  5012.2 1850.74  5015.7 1850.74    5016 1851.24  5022.4 1857.45  5030.7 1862.49
  5036.3 1864.29  5044.7 1867.59  5053.1 1870.55  5058.7 1871.63  5067.1 1873.92
  5075.5  1876.5  5081.1 1878.08  5103.4 1882.58    5109 1884.02  5111.8 1884.02
#Mann= 3 ,-1 , 0
    4900     .07       0    5012     .05       0    5016     .07       0
#XS Ineff= 2 , 0
          5002.3 1855.43
Permanent Ineff=
       F       F
Bank Sta=5012,5016
XS Rating Curve= 0 ,0
Exp/Cntr=0.3,0.1

Type RM Length L Ch R = 1 ,2376    ,487,487,487
BEGIN DESCRIPTION:
Stream0041 5.0
END DESCRIPTION:
XS GIS Cut Line= 3
      1950074.99     13915975.03        1950125.       13915875.
        1950125.     13915825.04
#Sta/Elev= 29
  4895.5 1871.42  4898.3 1871.42  4903.9 1868.81  4909.5 1867.97  4917.9 1864.97
  4926.3 1861.02  4931.9 1861.27  4940.3 1856.96  4948.6 1848.58  4954.2 1850.78
  4962.6 1843.01    4969 1831.31  4969.3 1830.81  4972.8 1830.81    4973 1831.31
  4976.6  1832.2    4985 1833.49  4993.4  1838.5    4999 1837.95  5004.5 1842.02
  5007.3 1842.02  5009.8 1842.02  5011.8 1843.33  5017.3 1846.93  5027.3 1848.43
  5037.3 1850.03  5047.3 1850.82  5054.8 1851.56  5057.3 1851.56
#Mann= 4 ,-1 , 0
  4895.5    .035       0    4969    .035       0    4973    .035       0
  5011.8     .07       0
#XS Ineff= 2 , 0
                         5004.85         1842.28
Permanent Ineff=
       F       F
Bank Sta=4969,4973
XS Rating Curve= 0 ,0
Exp/Cntr=0.3,0.1

Type RM Length L Ch R = 1 ,1889    ,452,452,452
BEGIN DESCRIPTION:
Stream0041 4.0
END DESCRIPTION:
XS GIS Cut Line= 3
      1950525.01     13916274.97        1950575.       13915975.
      1950674.99     13915775.01
#Sta/Elev= 30
  4692.1 1875.57  4716.6 1871.79  4719.9 1870.67    4725 1871.13    4763 1862.44
  4815.8 1852.73  4884.7 1842.94  4902.4 1837.09  4907.5 1837.12  4914.9 1832.51
  4925.2  1829.4  4968.3 1826.86  4986.1 1823.11  5004.6 1821.37  5008.2 1819.92
  5008.4 1819.42  5012.2 1819.92  5018.6 1823.72    5027 1825.58  5032.7 1825.17
  5085.6 1824.68  5099.6 1825.82  5116.4 1836.77    5122 1836.91  5138.8 1852.08
  5144.3  1852.8  5161.1  1862.1  5166.7 1862.84  5191.9 1872.35  5219.8 1878.03
#Mann= 7 ,-1 , 0
  4692.1     .07       0  4716.6    .035       0  4815.8     .07       0
  4914.9    .035       0  5008.2    .035       0  5012.2    .035       0
  5032.7      .1       0
Bank Sta=5008.2,5012.2
XS Rating Curve= 0 ,0
Exp/Cntr=0.3,0.1

Type RM Length L Ch R = 1 ,1437    ,449,449,449
BEGIN DESCRIPTION:
Stream0041 3.0
END DESCRIPTION:
XS GIS Cut Line= 3
      1950625.02     13916374.98        1950875.       13916175.
      1951075.02     13915974.98
#Sta/Elev= 30
  4675.1 1878.77  4678.3 1878.77  4696.7 1874.75  4710.1 1873.76  4731.9 1869.83
  4752.7 1862.45  4760.7 1860.72  4782.8 1853.53  4831.1 1838.17    4860 1830.76
  4888.8 1827.52  4912.3 1826.88  4959.2 1824.16  4973.6  1820.7  4981.6 1816.87
    4988 1816.63    4990 1811.45  4990.3 1810.95    4994 1811.45  4998.8 1811.45
  5011.1 1814.71  5023.5 1818.38  5051.8 1817.39  5065.9 1824.95  5080.1 1834.44
  5122.5  1858.4  5150.8 1871.71  5249.8 1905.05  5274.5 1909.79  5278.1 1909.79
#Mann= 7 ,-1 , 0
  4675.1     .07       0  4710.1    .035       0  4782.8      .1       0
  4912.3    .035       0    4990    .035       0    4994    .035       0
  5011.1      .1       0
Bank Sta=4990,4994
XS Rating Curve= 0 ,0
Exp/Cntr=0.3,0.1

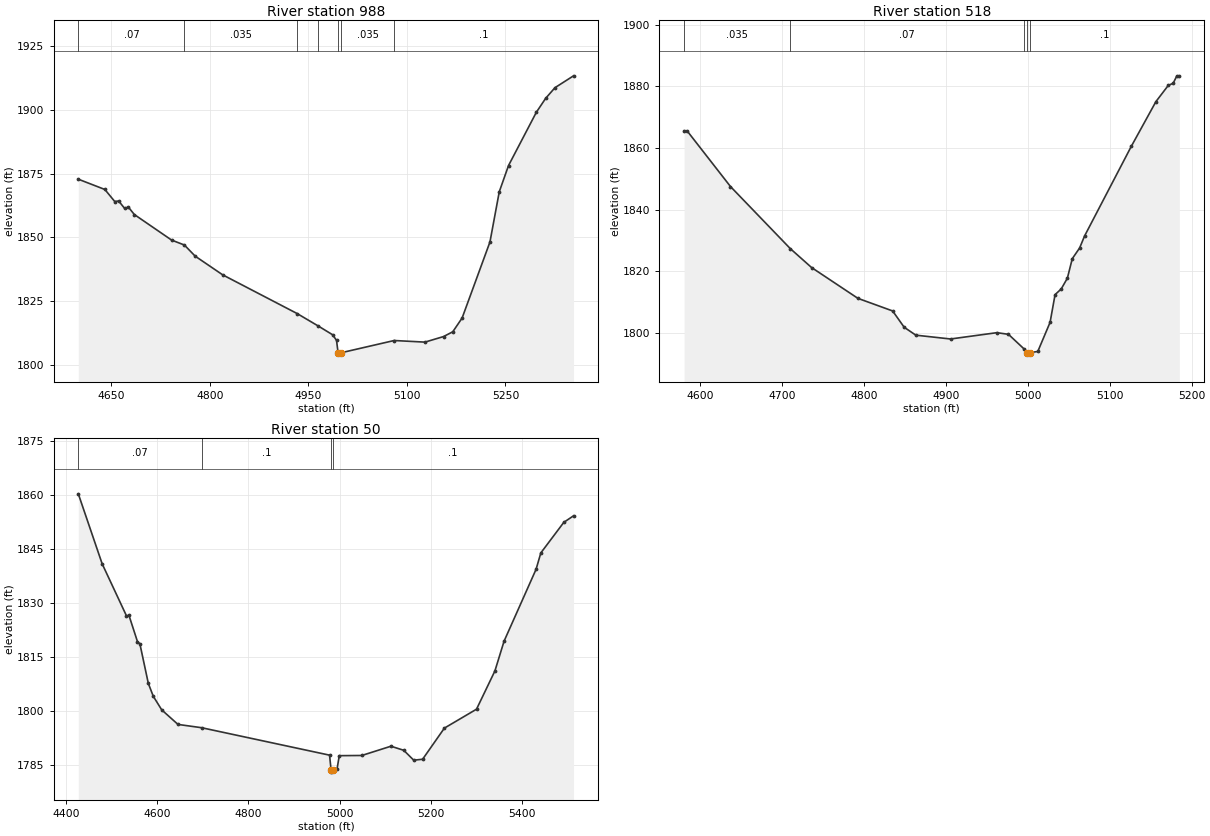
Type RM Length L Ch R = 1 ,988     ,470,470,470
BEGIN DESCRIPTION:
Stream0041 2.0
END DESCRIPTION:
XS GIS Cut Line= 3
      1950794.34      13916751.4        1951125.       13916525.
      1951375.01     13916274.99
#Sta/Elev= 30
  4599.5 1872.86    4640 1868.82    4655 1864.11    4661 1864.31  4669.9 1861.45
  4675.9 1861.88  4684.8 1859.01  4741.6 1848.98  4761.1 1847.04  4777.5 1842.68
  4819.4 1835.35    4933 1820.14  4964.9 1815.29  4986.7 1811.87  4992.8 1809.67
  4995.2 1804.75  4995.5 1804.25  4999.2 1804.75  5080.6 1809.59  5127.5 1808.96
  5155.8 1811.14  5169.9 1813.02  5184.1 1818.41  5226.5 1848.23  5240.7 1867.93
  5254.8 1878.22  5297.2 1899.12  5311.4 1904.59  5325.5 1908.74  5353.8  1913.4
#Mann= 7 ,-1 , 0
  4599.5     .07       0  4761.1    .035       0    4933     .07       0
  4964.9    .035       0  4995.2    .035       0  4999.2    .035       0
  5080.6      .1       0
Bank Sta=4995.2,4999.2
XS Rating Curve= 0 ,0
Exp/Cntr=0.3,0.1

Type RM Length L Ch R = 1 ,518     ,468,468,468
BEGIN DESCRIPTION:
Stream0041 1.0
END DESCRIPTION:
XS GIS Cut Line= 3
      1951224.97     13917025.03        1951525.       13916725.
      1951625.01     13916574.99
#Sta/Elev= 30
  4580.3  1865.6  4583.9  1865.6  4636.9 1847.53  4709.9  1827.4  4735.9 1821.26
  4792.5 1811.26  4834.9 1807.17    4849 1801.88  4863.2 1799.32  4905.6 1798.08
  4962.2 1800.13  4976.3 1799.59    4995 1794.94  4999.1 1793.67  4999.3 1793.17
  5003.1 1793.67  5012.1 1794.03  5027.1 1803.47  5033.2 1812.47  5040.7 1814.31
  5048.2 1817.79  5054.2 1824.12  5063.2 1827.61  5069.2 1831.48  5126.3 1860.58
  5156.3 1875.06  5171.4 1880.32  5177.4 1881.03  5181.9 1883.43  5184.9 1883.43
#Mann= 5 ,-1 , 0
  4580.3    .035       0  4709.9     .07       0    4995      .1       0
  4999.1     .05       0  5003.1      .1       0
Bank Sta=4999.1,5003.1
XS Rating Curve= 0 ,0
Exp/Cntr=0.3,0.1

Type RM Length L Ch R = 1 ,50      ,0,0,0
BEGIN DESCRIPTION:
Stream0041 0.0
END DESCRIPTION:
XS GIS Cut Line= 4
      1951312.93     13917210.44      1951833.67     13916996.23
      1951959.23     13916855.01      1951921.14     13916523.84
#Sta/Elev= 30
  4427.5 1860.27  4479.8 1840.84  4533.1  1826.4  4538.5 1826.55  4557.1 1819.27
  4562.5 1818.62    4581 1807.63  4591.9 1804.06  4610.4 1800.29    4646 1796.26
  4697.7 1795.35  4978.2 1787.73  4981.6 1783.52  4981.9 1783.02  4985.6 1783.52
  4994.7 1783.96  4999.5 1787.59  5048.8 1787.64  5112.7 1790.21  5140.8 1789.08
  5162.6 1786.34  5182.1 1786.59  5229.9 1795.24  5300.3 1800.49  5340.6 1811.11
  5360.7 1819.38  5430.8 1839.32  5441.3 1843.88  5491.6 1852.35  5512.9 1854.17
#Mann= 4 ,-1 , 0
  4427.5     .07       0  4697.7      .1       0  4981.6     .05       0
  4985.6      .1       0
Bank Sta=4981.6,4985.6
XS Rating Curve= 0 ,0
Exp/Cntr=0.3,0.1

Chan Stop Cuts=-1
Use User Specified Reach Order=0
Composite Channel Slope=5