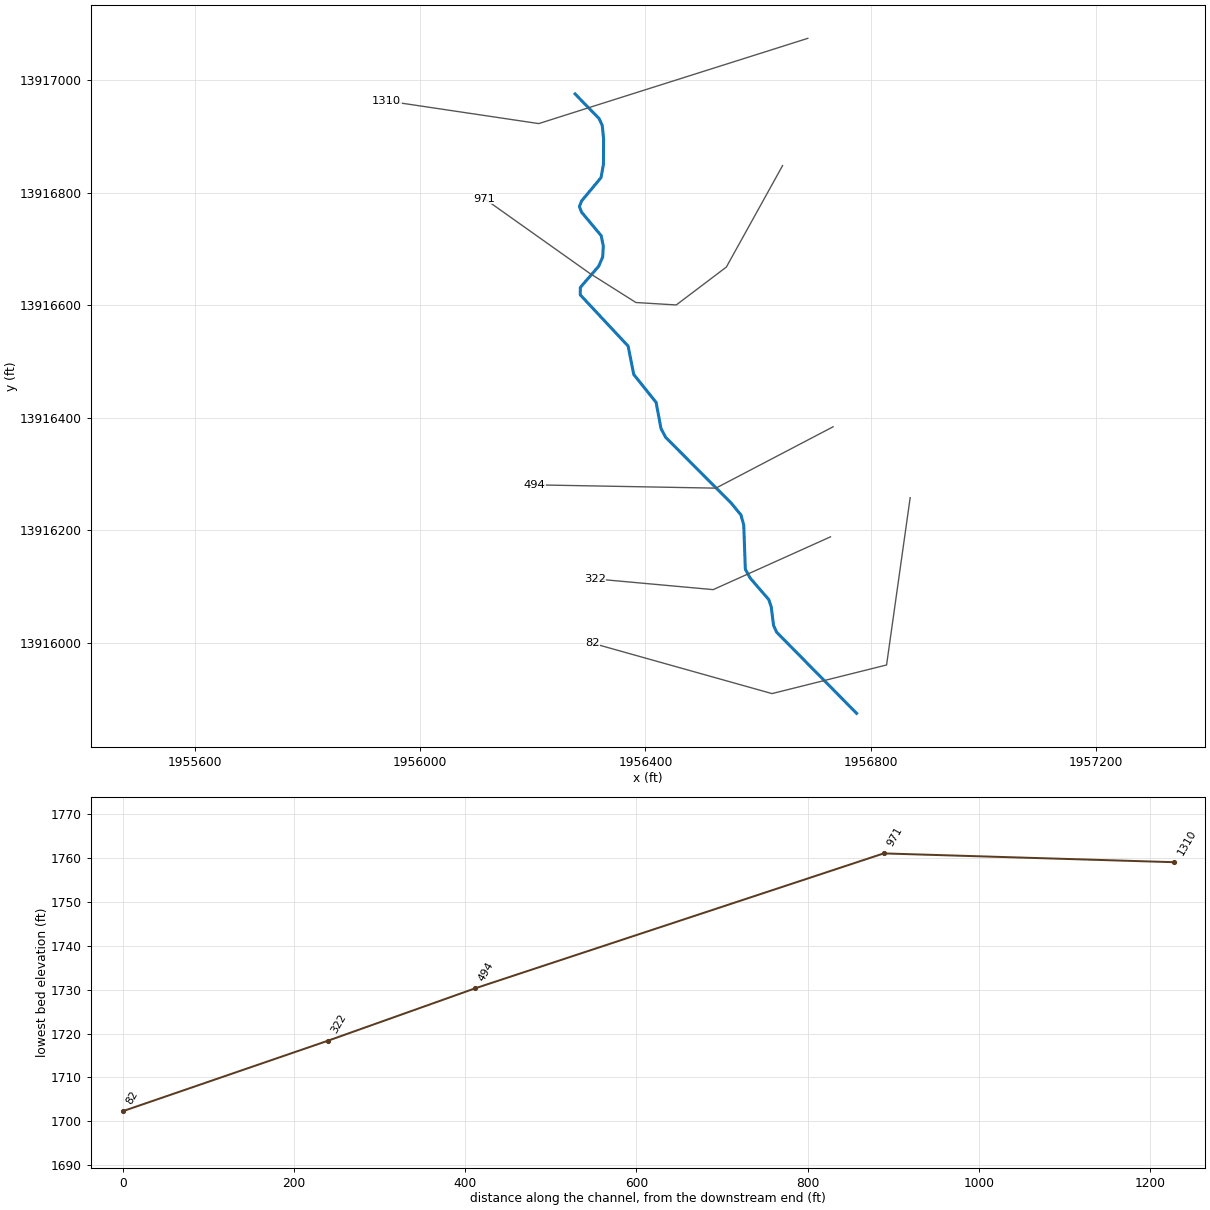
--- Stream0044.prj (project) ---

Proj Title=Stream0044 Base Level Engineering
Current Plan=p01
Default Exp/Contr=0.3,0.1
English Units
Geom File=g01
Flow File=f01
Plan File=p01
BEGIN DESCRIPTION:
Stream0044
END DESCRIPTION:

--- Stream0044.p01 (plan) ---

Plan Title=Multiple Run
Short Identifier=Multiple
Geom File=g01
Flow File=f01
Subcritical Flow
K Sum by GR= 0
Std Step Tol= 0.01
Critical Tol= 0.01
Num of Std Step Trials= 20
Max Error Tol= 0.3
Flow Tol Ratio= 0.001
Split Flow NTrial= 30
Split Flow Tol= 0.02
Split Flow Ratio= 0.02
Log Output Level= 0
Friction Slope Method= 1
Unsteady Friction Slope Method= 2
Unsteady Bridges Friction Slope Method= 1
Parabolic Critical Depth
Global Vel Dist=  1 , 1 , 1
Global Log Level= 0
CheckData=True
Encroach Param= -1, 0, 0, 0
BEGIN DESCRIPTION:
Multiple Run
END DESCRIPTION:

--- Stream0044.f01 (steady flow) ---

Flow Title=Multiple
Number of Profiles=7
Profile Names=10-year,25-year,50-year,1pct_min,100-year,1pct_plu,500-year
River Rch & RM= Stream0044,Reach-1,1310
     275     424     554     353     704    1405    1113
Boundary for River Rch & Prof#=Stream0044,Reach-1,1
Up Type=0
Dn Type=3
Dn Slope=0.005
Boundary for River Rch & Prof#=Stream0044,Reach-1,2
Up Type=0
Dn Type=3
Dn Slope=0.005
Boundary for River Rch & Prof#=Stream0044,Reach-1,3
Up Type=0
Dn Type=3
Dn Slope=0.005
Boundary for River Rch & Prof#=Stream0044,Reach-1,4
Up Type=0
Dn Type=3
Dn Slope=0.005
Boundary for River Rch & Prof#=Stream0044,Reach-1,5
Up Type=0
Dn Type=3
Dn Slope=0.005
Boundary for River Rch & Prof#=Stream0044,Reach-1,6
Up Type=0
Dn Type=3
Dn Slope=0.005
Boundary for River Rch & Prof#=Stream0044,Reach-1,7
Up Type=0
Dn Type=3
Dn Slope=0.005

--- Stream0044.g01 (geometry) ---

Geom Title=Existing Conditions

River Reach=Stream0044,Reach-1
Reach XY= 30
      1956275.00     13916975.00      1956317.64     13916931.32
      1956323.22     13916919.16      1956325.62     13916895.03
      1956325.32     13916849.94      1956321.07     13916826.49
      1956286.49     13916784.90      1956282.59     13916774.99
      1956286.53     13916765.07      1956321.36     13916723.35
      1956325.10     13916704.84      1956324.01     13916685.64
      1956316.84     13916668.95      1956284.34     13916631.55
      1956284.17     13916618.28      1956369.14     13916527.30
      1956379.19     13916476.74      1956418.90     13916427.19
      1956427.50     13916381.04      1956435.77     13916365.32
      1956552.12     13916248.52      1956569.48     13916227.43
      1956574.48     13916209.78      1956577.33     13916130.97
      1956585.84     13916115.35      1956618.86     13916077.17
      1956623.28     13916064.29      1956627.49     13916031.03
      1956633.13     13916018.94      1956775.00     13915875.00

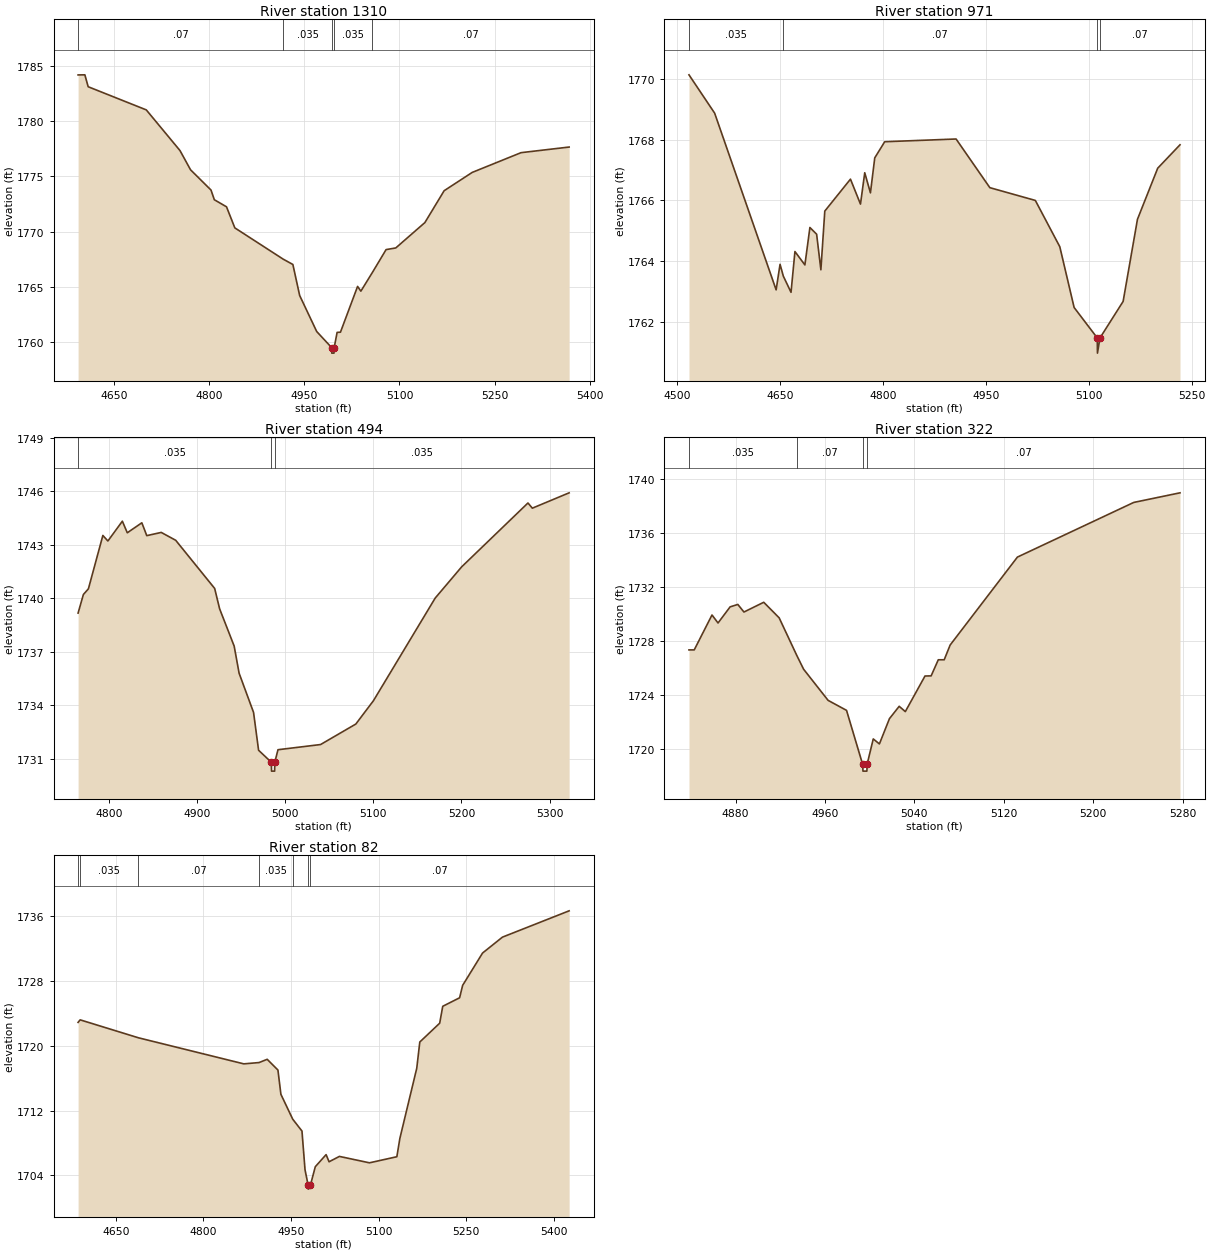
Type RM Length L Ch R = 1,1310,339,339,339
BEGIN DESCRIPTION:
Stream044 3.0
END DESCRIPTION:
XS GIS Cut Line= 4
      1956688.31     13917073.81      1956321.26     13916957.61
      1956210.46     13916922.40      1955939.91     13916962.69
#Sta/Elev= 30
  4592.9 1784.21  4603.6 1784.22  4608.8 1783.14  4700.5 1781.04  4753.7 1777.35
  4770.3 1775.61  4802.6 1773.77  4807.9 1772.89  4827.1 1772.25  4840.2 1770.34
  4916.6 1767.50  4931.8 1767.02  4942.5 1764.21  4969.4 1760.94  4993.0 1759.48
  4993.2 1758.98  4996.7 1758.98  4997.0 1759.48  5001.6 1760.86  5006.9 1760.88
  5033.9 1765.03  5039.1 1764.60  5057.1 1766.28  5078.9 1768.37  5094.2 1768.52
  5140.1 1770.82  5170.5 1773.71  5214.8 1775.37  5291.8 1777.16  5367.7 1777.67
#Mann=5,-1,0
  4592.9    0.07       0  4916.6   0.035       0  4993.0   0.035       0
  4997.0   0.035       0  5057.1    0.07       0
Bank Sta=4993,4997
Exp/Cntr=0.3,0.1

Type RM Length L Ch R = 1,971,477,477,477
BEGIN DESCRIPTION:
Stream0044 2.0
END DESCRIPTION:
XS GIS Cut Line= 6
      1956643.43     13916847.69      1956543.62     13916667.60
      1956454.64     13916600.32      1956383.03     13916604.66
      1956300.56     13916656.75      1956113.96     13916789.10
#Sta/Elev= 30
  4517.5 1770.13  4554.9 1768.87  4644.5 1763.06  4650.2 1763.90  4655.0 1763.51
  4666.2 1762.98  4671.9 1764.32  4686.4 1763.88  4693.7 1765.11  4703.5 1764.89
  4709.7 1763.72  4715.4 1765.65  4752.8 1766.70  4767.4 1765.88  4773.6 1766.91
  4781.9 1766.25  4788.2 1767.40  4802.7 1767.93  4906.7 1768.02  4955.9 1766.42
  5022.2 1766.00  5057.8 1764.48  5078.7 1762.48  5112.4 1761.48  5112.7 1760.98
  5116.4 1761.48  5150.1 1762.68  5171.0 1765.38  5200.5 1767.06  5233.0 1767.83
#Mann=4,-1,0
  4517.5   0.035       0  4655.0    0.07       0  5112.4    0.05       0
  5116.4    0.07       0
Bank Sta=5112.4,5116.4
Exp/Cntr=0.3,0.1

Type RM Length L Ch R = 1,494,172,172,172
BEGIN DESCRIPTION:
Stream0044 1.0
END DESCRIPTION:
XS GIS Cut Line= 3
      1956733.18     13916383.94      1956525.00     13916275.00
      1956203.11     13916280.84
#Sta/Elev= 30
  4765.3 1739.16  4771.3 1740.20  4777.0 1740.52  4793.4 1743.51  4799.1 1743.20
  4815.5 1744.31  4821.1 1743.66  4837.6 1744.22  4843.2 1743.50  4859.6 1743.68
  4876.0 1743.24  4920.2 1740.54  4925.8 1739.40  4942.3 1737.31  4947.9 1735.79
  4964.3 1733.59  4970.0 1731.47  4984.4 1730.80  4984.7 1730.30  4988.2 1730.30
  4988.4 1730.80  4992.0 1731.50  5040.3 1731.79  5080.3 1732.94  5100.3 1734.25
  5170.3 1740.00  5200.3 1741.75  5275.5 1745.33  5280.5 1745.04  5322.2 1745.90
#Mann=3,-1,0
  4765.3   0.035       0  4984.4   0.035       0  4988.4   0.035       0
Bank Sta=4984.4,4988.4
Exp/Cntr=0.3,0.1

Type RM Length L Ch R = 1,322,240,240,240
BEGIN DESCRIPTION:
Mapping XS e6371343
END DESCRIPTION:
XS GIS Cut Line= 3
      1956728.56     13916188.52      1956520.23     13916094.77
      1956310.14     13916113.87
#Sta/Elev= 30
  4838.3 1727.34  4843.0 1727.34  4858.9 1729.92  4864.3 1729.33  4875.1 1730.52
  4882.0 1730.70  4887.5 1730.14  4905.2 1730.86  4919.0 1729.71  4934.9 1726.91
  4940.9 1725.91  4962.8 1723.61  4979.3 1722.87  4993.7 1718.88  4994.0 1718.38
  4997.5 1718.38  4997.7 1718.88  5003.2 1720.76  5008.7 1720.39  5017.7 1722.26
  5026.4 1723.17  5031.9 1722.78  5049.5 1725.41  5055.0 1725.42  5061.4 1726.61
  5066.7 1726.61  5072.0 1727.70  5132.2 1734.20  5236.3 1738.24  5277.7 1738.95
#Mann=4,-1,0
  4838.3   0.035       0  4934.9    0.07       0  4993.7    0.05       0
  4997.7    0.07       0
Bank Sta=4993.7,4997.7
Exp/Cntr=0.3,0.1

Type RM Length L Ch R = 1,82,0,0,0
BEGIN DESCRIPTION:
Stream0044 0.0
END DESCRIPTION:
XS GIS Cut Line= 4
      1956870.07     13916258.03      1956828.16     13915960.96
      1956624.68     13915910.13      1956305.64     13915999.63
#Sta/Elev= 30
  4585.2 1722.86  4588.8 1723.17  4688.6 1720.96  4869.0 1717.75  4895.2 1717.91
  4909.1 1718.31  4927.5 1716.99  4932.6 1714.00  4952.8 1710.94  4968.7 1709.47
  4973.9 1704.71  4979.2 1702.82  4979.5 1702.32  4983.2 1702.82  4991.5 1705.08
  5010.0 1706.57  5015.1 1705.69  5032.8 1706.35  5084.3 1705.56  5131.2 1706.31
  5136.4 1708.58  5165.3 1717.21  5170.5 1720.44  5204.6 1722.76  5209.8 1724.84
  5238.7 1725.89  5243.9 1727.42  5278.0 1731.40  5312.1 1733.36  5426.3 1736.60
#Mann=7,-1,0
  4585.2    0.07       0  4588.8   0.035       0  4688.6    0.07       0
  4895.2   0.035       0  4952.8    0.07       0  4979.2    0.05       0
  4983.2    0.07       0
Bank Sta=4979.2,4983.2
Exp/Cntr=0.3,0.1

Chan Stop Cuts=-1