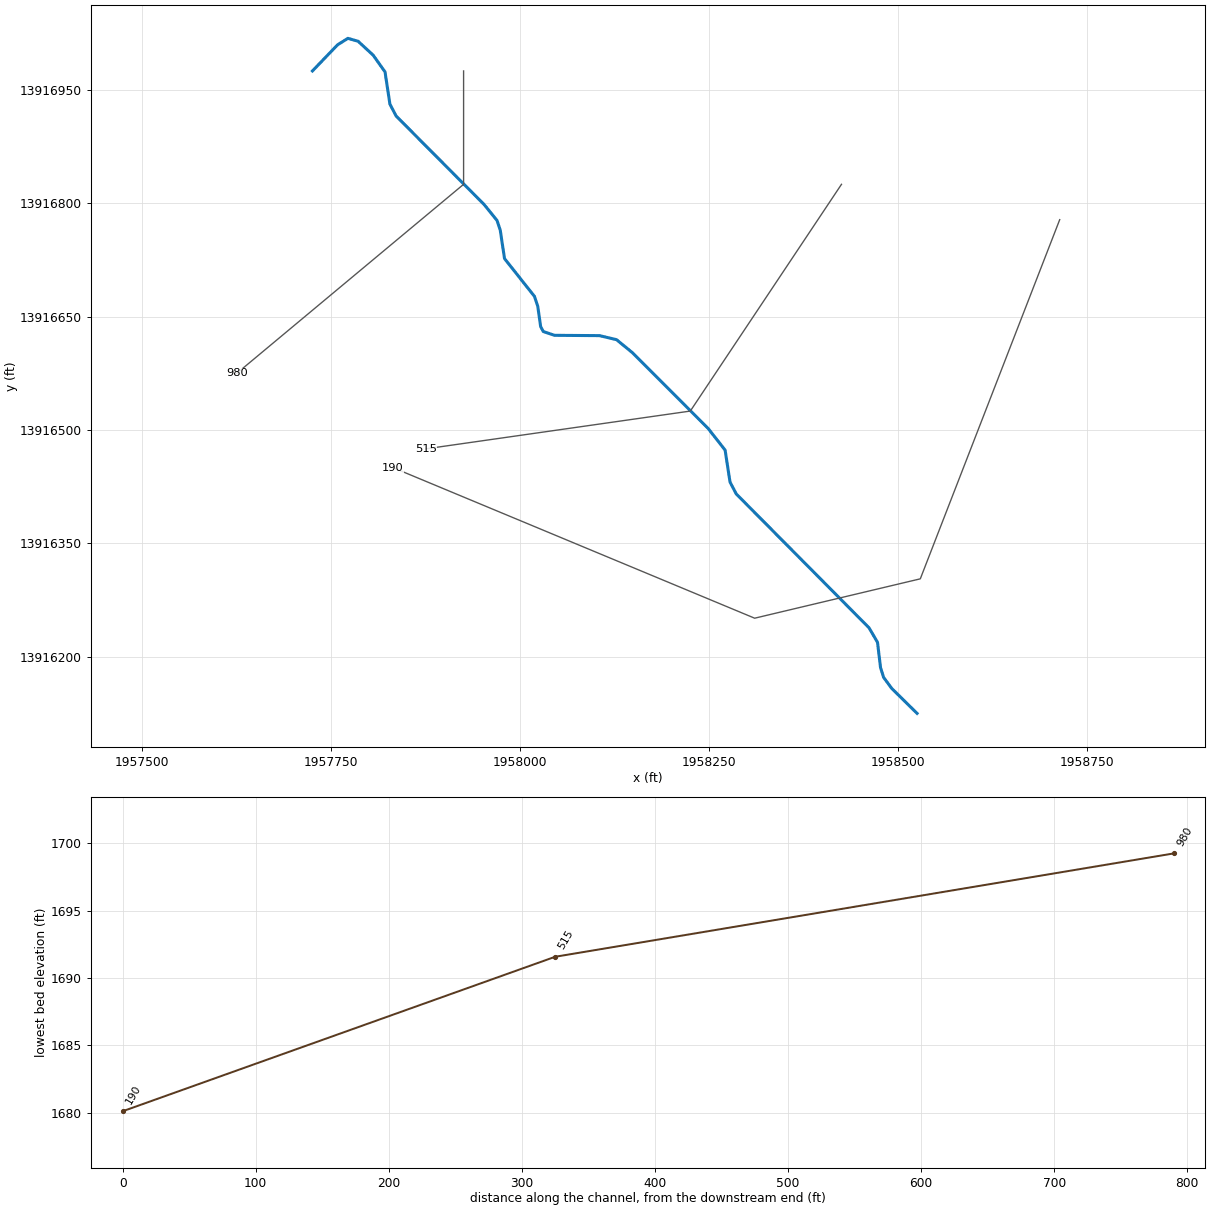
--- Stream0045.prj (project) ---

Proj Title=Stream0045 Base Level Engineering
Current Plan=p01
Default Exp/Contr=0.3,0.1
English Units
Geom File=g01
Flow File=f01
Plan File=p01
BEGIN DESCRIPTION:
Stream0045
END DESCRIPTION:

--- Stream0045.p01 (plan) ---

Plan Title=Multiple Run
Short Identifier=Multiple
Geom File=g01
Flow File=f01
Subcritical Flow
K Sum by GR= 0
Std Step Tol= 0.01
Critical Tol= 0.01
Num of Std Step Trials= 20
Max Error Tol= 0.3
Flow Tol Ratio= 0.001
Split Flow NTrial= 30
Split Flow Tol= 0.02
Split Flow Ratio= 0.02
Log Output Level= 0
Friction Slope Method= 1
Unsteady Friction Slope Method= 2
Unsteady Bridges Friction Slope Method= 1
Parabolic Critical Depth
Global Vel Dist=  1 , 1 , 1
Global Log Level= 0
CheckData=True
Encroach Param= -1, 0, 0, 0
BEGIN DESCRIPTION:
Multiple Run
END DESCRIPTION:

--- Stream0045.f01 (steady flow) ---

Flow Title=Multiple
Number of Profiles=7
Profile Names=10-year,25-year,50-year,1pct_min,100-year,1pct_plu,500-year
River Rch & RM= Stream0045,Reach-1,980
    1185    2018    2812    1896    3782    7547    6749
Boundary for River Rch & Prof#=Stream0045,Reach-1,1
Up Type=0
Dn Type=3
Dn Slope=0.005
Boundary for River Rch & Prof#=Stream0045,Reach-1,2
Up Type=0
Dn Type=3
Dn Slope=0.005
Boundary for River Rch & Prof#=Stream0045,Reach-1,3
Up Type=0
Dn Type=3
Dn Slope=0.005
Boundary for River Rch & Prof#=Stream0045,Reach-1,4
Up Type=0
Dn Type=3
Dn Slope=0.005
Boundary for River Rch & Prof#=Stream0045,Reach-1,5
Up Type=0
Dn Type=3
Dn Slope=0.005
Boundary for River Rch & Prof#=Stream0045,Reach-1,6
Up Type=0
Dn Type=3
Dn Slope=0.005
Boundary for River Rch & Prof#=Stream0045,Reach-1,7
Up Type=0
Dn Type=3
Dn Slope=0.005

--- Stream0045.g01 (geometry) ---

Geom Title=Existing Conditions

River Reach=Stream0045,Reach-1
Reach XY= 30
      1957725.00     13916975.00      1957758.36     13917009.67
      1957771.92     13917018.16      1957785.41     13917014.28
      1957805.29     13916995.94      1957821.05     13916973.78
      1957827.52     13916931.11      1957835.77     13916915.35
      1957951.99     13916798.47      1957969.17     13916777.30
      1957973.49     13916764.37      1957979.18     13916726.70
      1958018.74     13916676.80      1958023.10     13916663.81
      1958026.96     13916636.72      1958030.44     13916630.25
      1958045.25     13916625.21      1958104.79     13916624.80
      1958127.37     13916619.45      1958148.51     13916602.12
      1958248.70     13916501.82      1958271.02     13916473.35
      1958277.53     13916431.05      1958285.78     13916415.32
      1958461.43     13916238.23      1958472.66     13916219.03
      1958476.66     13916185.69      1958480.71     13916172.65
      1958491.42     13916158.08      1958525.00     13916125.00

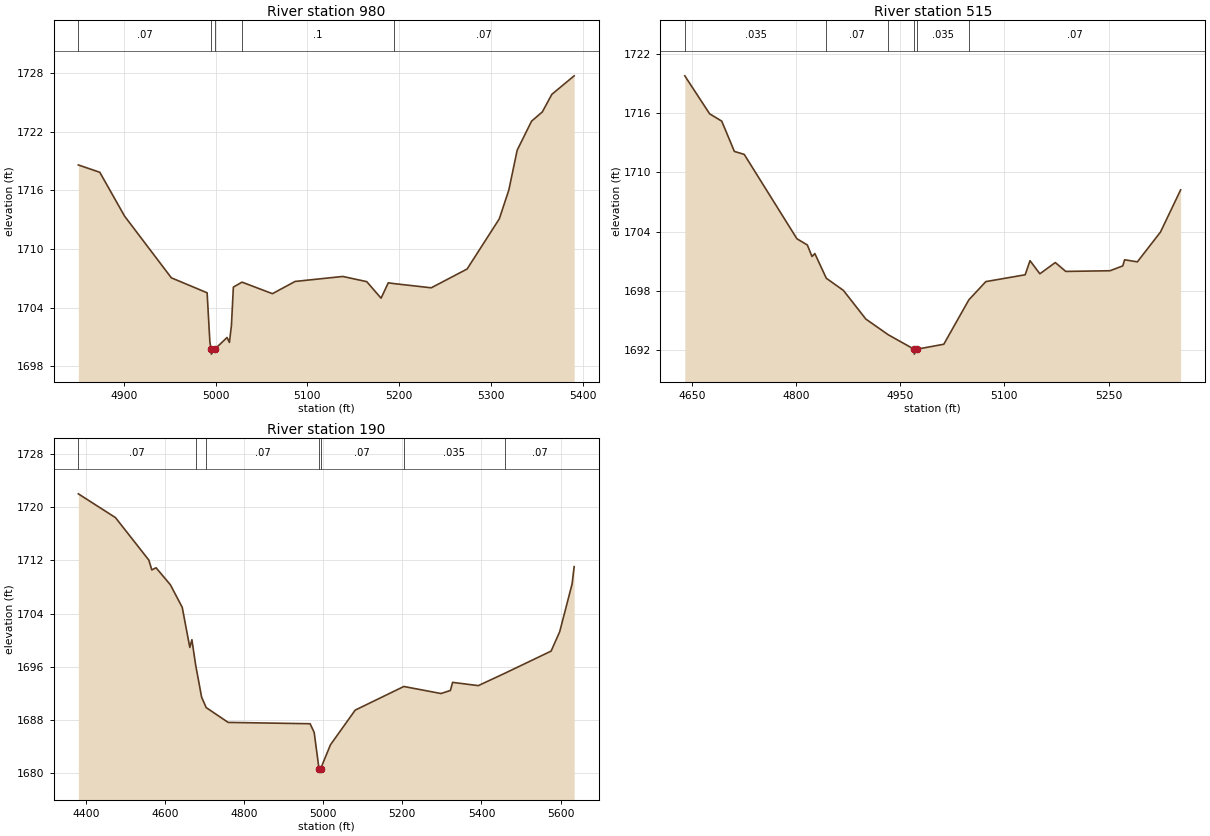
Type RM Length L Ch R = 1,980,465,465,465
BEGIN DESCRIPTION:
Stream0045 2.0
END DESCRIPTION:
XS GIS Cut Line= 3
      1957925.00     13916975.02      1957925.00     13916825.00
      1957625.03     13916575.02
#Sta/Elev= 30
  4850.3 1718.59  4873.7 1717.84  4900.7 1713.36  4951.7 1707.05  4990.7 1705.52
  4993.7 1700.49  4995.0 1699.75  4995.3 1699.25  4999.0 1699.75  5012.4 1700.95
  5015.0 1700.45  5017.2 1702.18  5019.3 1706.10  5028.7 1706.61  5061.9 1705.43
  5086.6 1706.68  5138.6 1707.19  5164.7 1706.66  5180.3 1704.97  5188.2 1706.54
  5194.3 1706.46  5235.0 1706.03  5274.1 1707.95  5309.2 1713.08  5319.6 1716.03
  5328.7 1720.10  5344.4 1723.07  5356.1 1724.01  5366.5 1725.81  5390.8 1727.70
#Mann=5,-1,0
  4850.3    0.07       0  4995.0    0.05       0  4999.0    0.07       0
  5028.7     0.1       0  5194.3    0.07       0
Bank Sta=4995,4999
Exp/Cntr=0.3,0.1

Type RM Length L Ch R = 1,515,325,325,325
BEGIN DESCRIPTION:
Stream0045 1.0
END DESCRIPTION:
XS GIS Cut Line= 3
      1958425.00     13916825.00      1958225.00     13916525.00
      1957875.01     13916475.00
#Sta/Elev= 30
  4639.7 1719.78  4675.5 1715.93  4692.9 1715.19  4711.1 1712.12  4725.3 1711.82
  4801.2 1703.27  4816.2 1702.64  4822.9 1701.47  4827.0 1701.77  4843.5 1699.27
  4868.1 1698.04  4900.5 1695.13  4932.8 1693.54  4969.9 1692.08  4970.2 1691.58
  4973.9 1692.08  5012.7 1692.58  5048.8 1697.08  5073.3 1698.93  5129.9 1699.62
  5136.9 1701.05  5151.1 1699.72  5173.3 1700.86  5188.4 1699.96  5252.1 1700.03
  5270.5 1700.52  5273.1 1701.14  5291.5 1700.93  5324.8 1703.95  5353.8 1708.22
#Mann=6,-1,0
  4639.7   0.035       0  4843.5    0.07       0  4932.8   0.035       0
  4969.9   0.035       0  4973.9   0.035       0  5048.8    0.07       0
Bank Sta=4969.9,4973.9
Exp/Cntr=0.3,0.1

Type RM Length L Ch R = 1,190,0,0,0
BEGIN DESCRIPTION:
Stream0045 T
END DESCRIPTION:
XS GIS Cut Line= 4
      1958713.74     13916778.23      1958529.29     13916303.02
      1958310.11     13916250.93      1957831.19     13916450.30
#Sta/Elev= 30
  4380.6 1722.04  4474.5 1718.46  4558.9 1712.06  4566.4 1710.58  4577.2 1710.90
  4613.4 1708.34  4643.3 1704.95  4662.5 1698.91  4667.8 1700.07  4677.1 1696.32
  4692.4 1691.40  4704.0 1689.84  4759.5 1687.61  4966.7 1687.41  4977.0 1686.10
  4989.2 1680.62  4989.4 1680.12  4993.2 1680.62  5018.1 1684.23  5080.7 1689.46
  5203.7 1693.02  5297.6 1691.96  5321.5 1692.42  5327.0 1693.64  5392.0 1693.15
  5458.7 1695.00  5576.1 1698.35  5597.8 1701.26  5629.2 1708.47  5634.4 1711.07
#Mann=7,-1,0
  4380.6    0.07       0  4677.1   0.035       0  4704.0    0.07       0
  4989.2    0.05       0  4993.2    0.07       0  5203.7   0.035       0
  5458.7    0.07       0
Bank Sta=4989.2,4993.2
Exp/Cntr=0.3,0.1

Chan Stop Cuts=-1