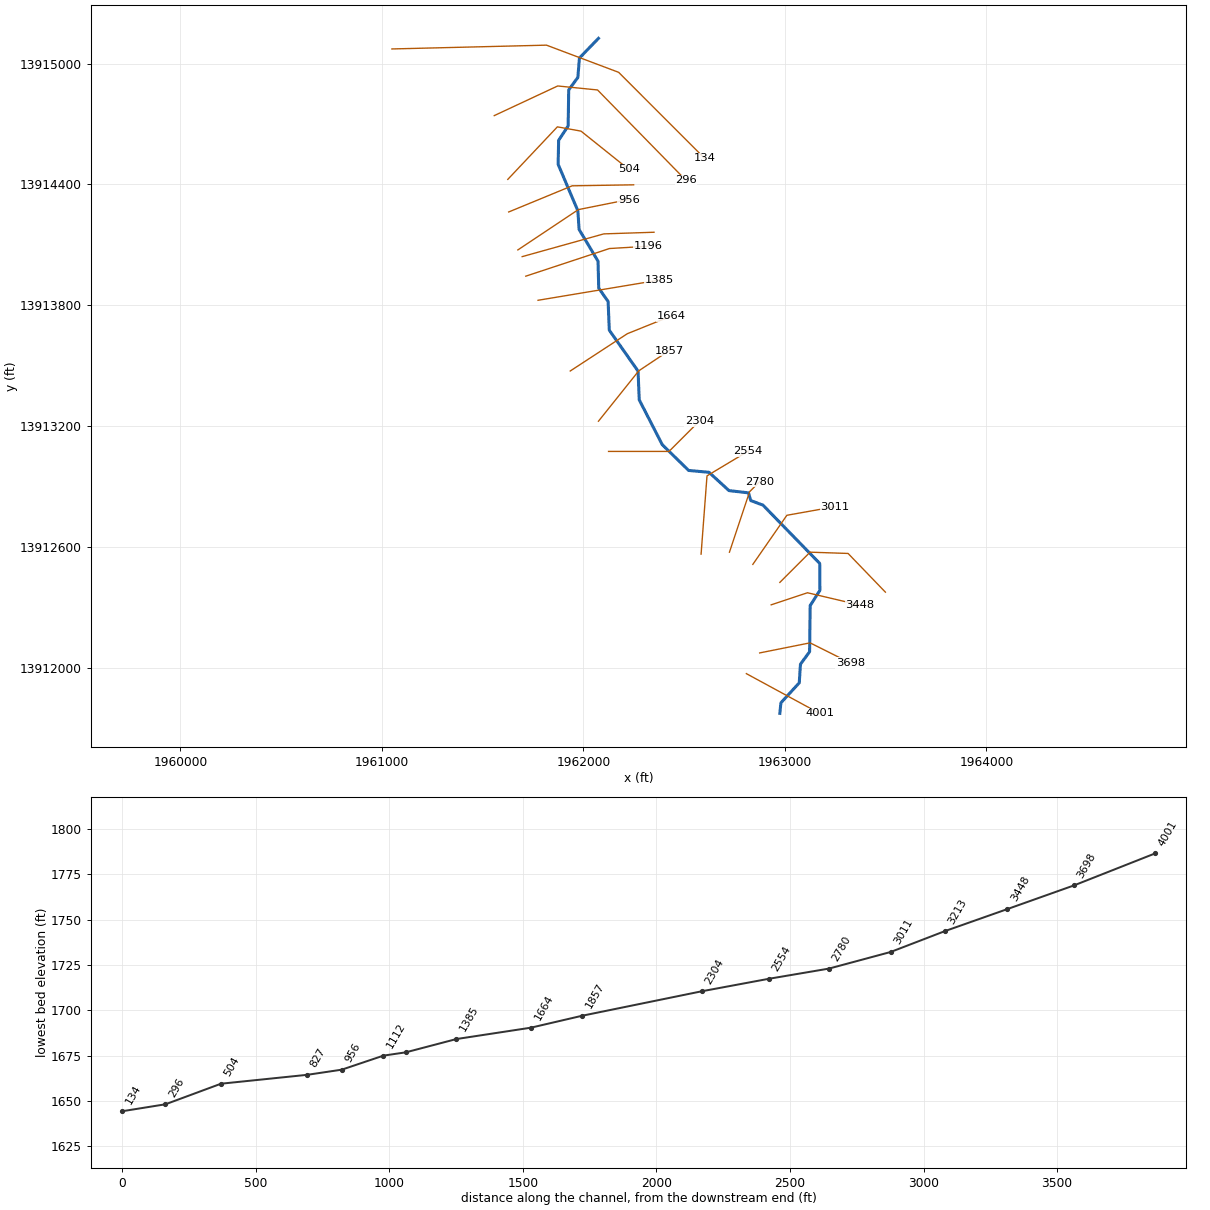
--- Stream0048.prj (project) ---

Proj Title=Stream0048 Base Level Engineering
Current Plan=p01
Default Exp/Contr=0.3,0.1
English Units
Geom File=g01
Flow File=f01
Plan File=p01
Y Axis Title=Elevation
X Axis Title(PF)=Main Channel Distance
X Axis Title(XS)=Station
BEGIN DESCRIPTION:
Stream0048
END DESCRIPTION:
DSS Export Rating Curves= 0
DSS Export Rating Curve Sorted= 0
DSS Export Volume Flow Curves= 0
DXF OffsetX= 0
DXF OffsetY= 0
DXF ScaleX= 1
DXF ScaleY= 10

--- Stream0048.p01 (plan) ---

Plan Title=Multiple Run
Short Identifier=Multiple
Geom File=g01
Flow File=f01
Subcritical Flow
K Sum by GR= 0
Std Step Tol= 0.01
Critical Tol= 0.01
Num of Std Step Trials= 20
Max Error Tol= 0.3
Flow Tol Ratio= 0.001
Split Flow NTrial= 30
Split Flow Tol= 0.02
Split Flow Ratio= 0.02
Log Output Level= 0
Friction Slope Method= 1
Unsteady Friction Slope Method= 2
Unsteady Bridges Friction Slope Method= 1
Parabolic Critical Depth
Global Vel Dist=  1 , 1 , 1
Global Log Level= 0
CheckData=True
Encroach Param= -1, 0, 0, 0
BEGIN DESCRIPTION:
Multiple Run
END DESCRIPTION:

--- Stream0048.f01 (steady flow) ---

Flow Title=Multiple
Number of Profiles=7
Profile Names=10-year,25-year,50-year,1pct_min,100-year,1pct_plu,500-year
River Rch & RM= Stream0048,Reach-1,4001
     187     281     362     228     454     906     698
River Rch & RM= Stream0048,Reach-1,3698
     696    1155    1584    1055    2105    4201    3658
Boundary for River Rch & Prof#=Stream0048,Reach-1,1
Up Type=0
Dn Type=3
Dn Slope=0.005
Boundary for River Rch & Prof#=Stream0048,Reach-1,2
Up Type=0
Dn Type=3
Dn Slope=0.005
Boundary for River Rch & Prof#=Stream0048,Reach-1,3
Up Type=0
Dn Type=3
Dn Slope=0.005
Boundary for River Rch & Prof#=Stream0048,Reach-1,4
Up Type=0
Dn Type=3
Dn Slope=0.005
Boundary for River Rch & Prof#=Stream0048,Reach-1,5
Up Type=0
Dn Type=3
Dn Slope=0.005
Boundary for River Rch & Prof#=Stream0048,Reach-1,6
Up Type=0
Dn Type=3
Dn Slope=0.005
Boundary for River Rch & Prof#=Stream0048,Reach-1,7
Up Type=0
Dn Type=3
Dn Slope=0.005

--- Stream0048.g01 (geometry) ---

Geom Title=Existing Conditions
Program Version=4.10

River Reach=Stream0048      ,Reach-1
Reach XY= 30
        1962975.       13911775.      1962980.33     13911827.51
      1963071.39      13911926.5      1963077.36     13912019.02
      1963122.74     13912080.94      1963125.52     13912309.78
      1963173.79     13912385.51      1963172.95     13912519.14
      1962891.49      13912808.3       1962830.8     13912831.05
      1962819.38     13912869.38      1962722.64     13912880.56
       1962623.5     13912971.37      1962522.57     13912980.52
      1962391.64     13913108.32      1962277.25     13913330.93
      1962271.45     13913473.53      1962128.76     13913676.56
      1962122.73     13913819.06      1962076.23     13913885.51
      1962072.75     13914019.07      1961978.83     13914176.58
      1961972.65     13914269.03      1961874.77     13914499.93
      1961877.25     13914619.06      1961924.48     13914690.22
      1961927.26     13914869.06      1961972.64     13914930.98
      1961980.46     13915027.45        1962075.       13915125.

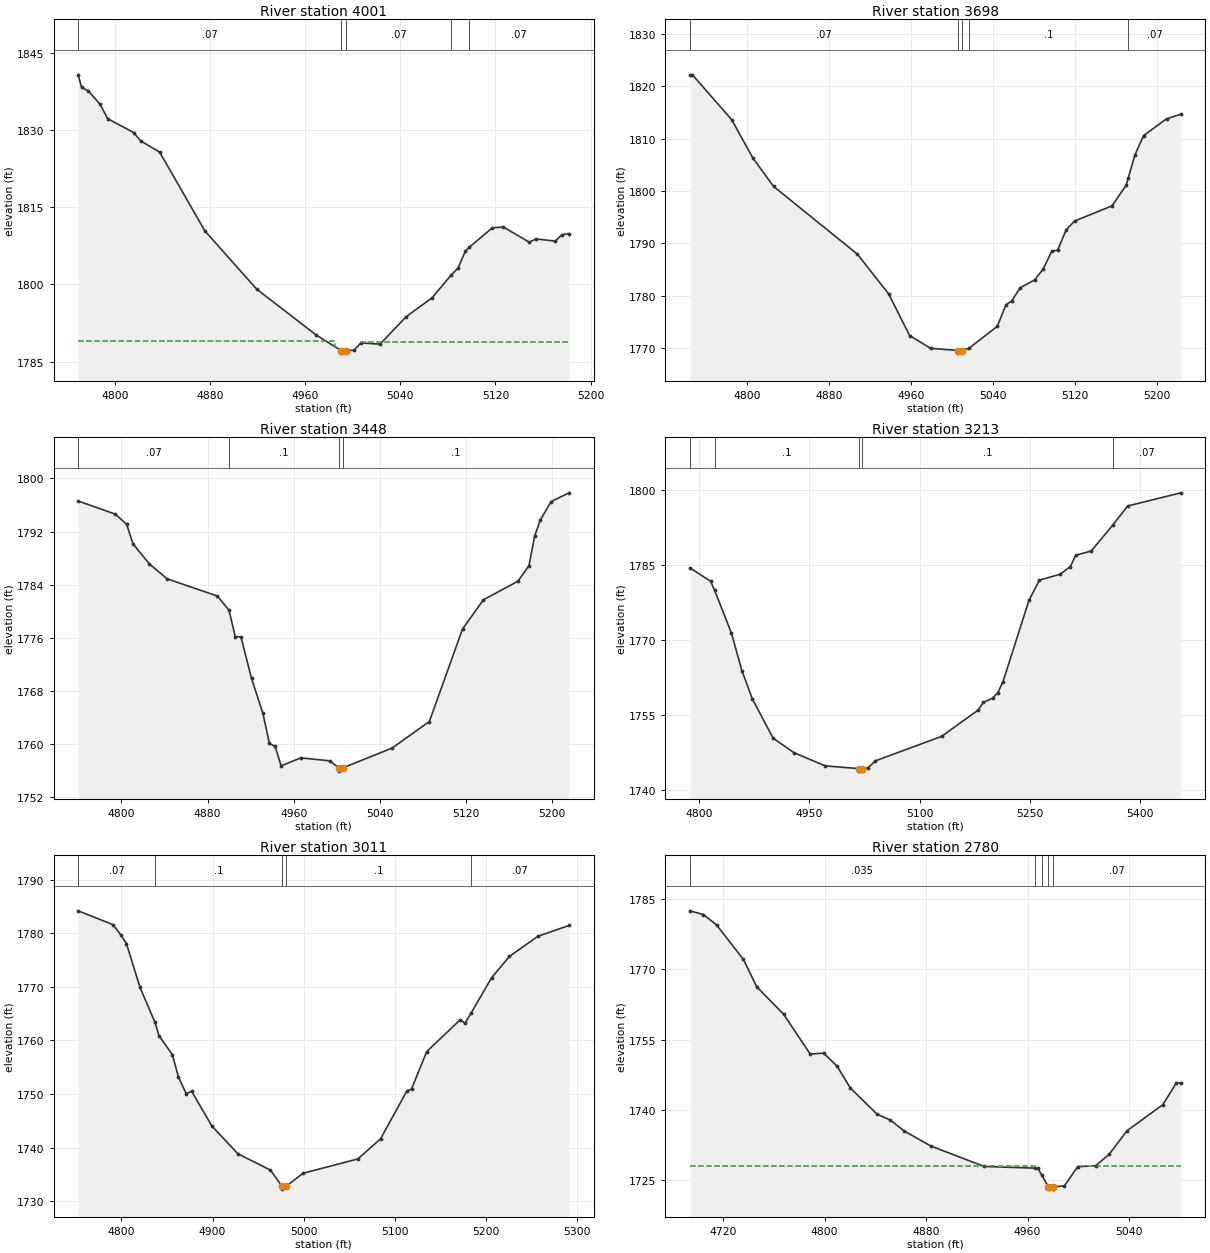
Type RM Length L Ch R = 1 ,4001    ,303,303,303
BEGIN DESCRIPTION:
Stream0048 9.0
END DESCRIPTION:
XS GIS Cut Line= 2
      1962808.85     13911972.25      1963171.73     13911775.26
#Sta/Elev= 30
    4769 1840.72    4772 1838.26  4777.7 1837.58  4787.4 1835.02  4793.9  1832.2
  4815.7  1829.5  4821.5  1827.9  4837.6  1825.7  4875.6 1810.39  4919.3 1799.04
  4969.4 1790.13  4990.2 1787.13  4990.4 1786.63  4994.2 1787.13  5001.1 1787.19
  5006.8 1788.62  5022.9 1788.37  5044.8 1793.68  5066.7 1797.39  5082.5 1801.74
  5088.5 1803.14  5094.6  1806.4  5097.7 1807.16  5117.3 1810.97  5126.5 1811.16
  5148.4 1808.19  5154.1 1808.83  5170.3  1808.4  5175.9 1809.65  5181.9 1809.84
#Mann= 5 ,-1 , 0
    4769     .07       0  4990.2     .05       0  4994.2     .07       0
  5082.5      .1       0  5097.7     .07       0
#XS Ineff= 2 , 0
         4985.19  1788.9 5006.62          1788.7
Permanent Ineff=
       F       F
Bank Sta=4990.2,4994.2
XS Rating Curve= 0 ,0
Exp/Cntr=0.3,0.1

Type RM Length L Ch R = 1 ,3698    ,250,250,250
BEGIN DESCRIPTION:
Stream0048 8.0
END DESCRIPTION:
XS GIS Cut Line= 3
        1962875.       13912075.        1963125.       13912125.
      1963325.04     13912024.98
#Sta/Elev= 30
  4744.6 1822.21  4747.1 1822.21  4785.4 1813.62  4805.8 1806.37  4826.2 1800.88
  4907.8 1787.95  4938.4 1780.33  4958.8 1772.38  4979.2 1769.94  5005.9 1769.52
  5006.2 1769.02  5009.9 1769.52  5016.7 1769.96  5044.3 1774.15  5052.7 1778.26
  5058.2 1778.97  5066.6 1781.51  5080.6    1783    5089  1785.1  5097.4 1788.51
    5103 1788.68  5111.4 1792.59  5119.7 1794.28  5156.1 1797.17    5170 1801.15
  5171.9 1802.45  5178.4 1806.89  5186.8 1810.58  5209.2  1813.8  5223.2 1814.68
#Mann= 5 ,-1 , 0
  4744.6     .07       0  5005.9     .05       0  5009.9     .07       0
  5016.7      .1       0  5171.9     .07       0
Bank Sta=5005.9,5009.9
XS Rating Curve= 0 ,0
Exp/Cntr=0.3,0.1

Type RM Length L Ch R = 1 ,3448    ,235,235,235
BEGIN DESCRIPTION:
Mapping XS 43fa77e3
END DESCRIPTION:
XS GIS Cut Line= 3
      1962932.16     13912313.77      1963112.19     13912373.58
      1963371.24     13912312.71
#Sta/Elev= 30
  4759.8  1796.6  4794.4 1794.62  4804.9 1793.09  4810.7 1790.16    4826 1787.13
  4842.4 1784.89  4889.2 1782.28  4899.9 1780.16  4905.7 1776.19    4911 1776.13
  4920.8 1769.89  4931.4 1764.61  4937.4  1760.1  4942.7 1759.65  4948.3 1756.72
  4966.5 1757.93  4993.5 1757.48  5001.7 1756.43    5002 1755.93  5005.7 1756.43
  5051.3  1759.4  5085.9  1763.4  5116.7 1777.33  5136.1 1781.73  5168.1 1784.52
  5178.4 1786.88  5183.6 1791.28  5188.8  1793.7  5198.9 1796.52  5215.6 1797.83
#Mann= 4 ,-1 , 0
  4759.8     .07       0  4899.9      .1       0  5001.7     .05       0
  5005.7      .1       0
Bank Sta=5001.7,5005.7
XS Rating Curve= 0 ,0
Exp/Cntr=0.3,0.1

Type RM Length L Ch R = 1 ,3213    ,202,202,202
BEGIN DESCRIPTION:
Stream0048 7.0
END DESCRIPTION:
XS GIS Cut Line= 4
      1962975.02     13912425.02        1963125.       13912575.
       1963313.7     13912568.66      1963498.82     13912376.67
#Sta/Elev= 30
  4787.5 1784.45  4815.7 1781.77    4821    1780    4844 1771.38  4858.2 1763.87
  4872.3 1758.23  4900.6 1750.33  4928.9 1747.42  4971.3 1744.77  5017.6 1744.21
  5017.9 1743.71  5021.4 1743.71  5021.6 1744.21  5029.6 1744.35  5039.6 1745.76
  5129.7 1750.67  5179.7 1755.97  5186.6 1757.51    5199 1758.33  5206.2 1759.45
  5213.1 1761.57  5248.6 1777.96  5262.8    1782  5290.8 1783.17  5304.9 1784.73
  5312.1 1786.98  5333.2 1787.84  5362.2 1792.98  5382.9 1796.87  5455.1  1799.5
#Mann= 5 ,-1 , 0
  4787.5     .07       0    4821      .1       0  5017.6     .05       0
  5021.6      .1       0  5362.2     .07       0
Bank Sta=5017.6,5021.6
XS Rating Curve= 0 ,0
Exp/Cntr=0.3,0.1

Type RM Length L Ch R = 1 ,3011    ,231,231,231
BEGIN DESCRIPTION:
Mapping XS 74dd5ac1
END DESCRIPTION:
XS GIS Cut Line= 3
      1962841.05     13912514.45       1963009.8     13912757.99
      1963248.81     13912800.74
#Sta/Elev= 30
  4752.4 1784.16  4790.7 1781.59  4799.4 1779.65  4805.5 1778.04  4820.4 1769.87
  4836.8 1763.37  4841.3 1760.87  4855.9 1757.35  4862.6 1753.18  4871.1 1750.06
  4877.1 1750.51  4899.1 1744.08  4927.8 1738.86  4963.6 1735.81  4976.5 1732.76
  4976.7 1732.26  4980.5 1732.76  4999.4 1735.22  5059.6 1737.89  5084.5 1741.64
  5113.4 1750.56  5118.5 1750.93  5135.2 1757.91  5172.2 1763.88  5177.3 1763.18
  5183.8 1765.06  5206.4 1771.67    5226 1775.66  5257.2 1779.41  5291.5 1781.43
#Mann= 5 ,-1 , 0
  4752.4     .07       0  4836.8      .1       0  4976.5     .05       0
  4980.5      .1       0  5183.8     .07       0
Bank Sta=4976.5,4980.5
XS Rating Curve= 0 ,0
Exp/Cntr=0.3,0.1

Type RM Length L Ch R = 1 ,2780    ,226,226,226
BEGIN DESCRIPTION:
Stream0048 6.0
END DESCRIPTION:
XS GIS Cut Line= 3
      1962724.99     13912574.97        1962825.       13912875.
      1962875.02     13912925.02
#Sta/Elev= 30
  4693.8 1782.47  4704.4 1781.68  4714.9 1779.44    4736  1772.1  4746.5 1766.26
  4767.6 1760.44  4788.7  1751.9  4799.2 1752.12  4809.8 1749.34  4820.3 1744.66
  4841.4 1739.07  4851.9 1737.82  4862.5 1735.55  4883.6 1732.31  4925.7 1727.94
  4965.5 1727.58  4967.9 1727.63  4971.2 1726.07  4976.4  1723.6  4976.7  1723.1
  4980.2  1723.1  4980.4  1723.6    4989  1723.8  4999.5 1727.89  5013.6 1728.09
  5024.2 1730.51  5038.3 1735.54  5066.6 1741.12  5077.2 1745.74  5080.8 1745.74
#Mann= 5 ,-1 , 0
  4693.8    .035       0  4965.5      .1       0  4971.2     .07       0
  4976.4     .05       0  4980.4     .07       0
#XS Ineff= 2 , 0
         4967.13 1727.96  5001.1          1728.1
Permanent Ineff=
       F       F
Bank Sta=4976.4,4980.4
XS Rating Curve= 0 ,0
Exp/Cntr=0.3,0.1

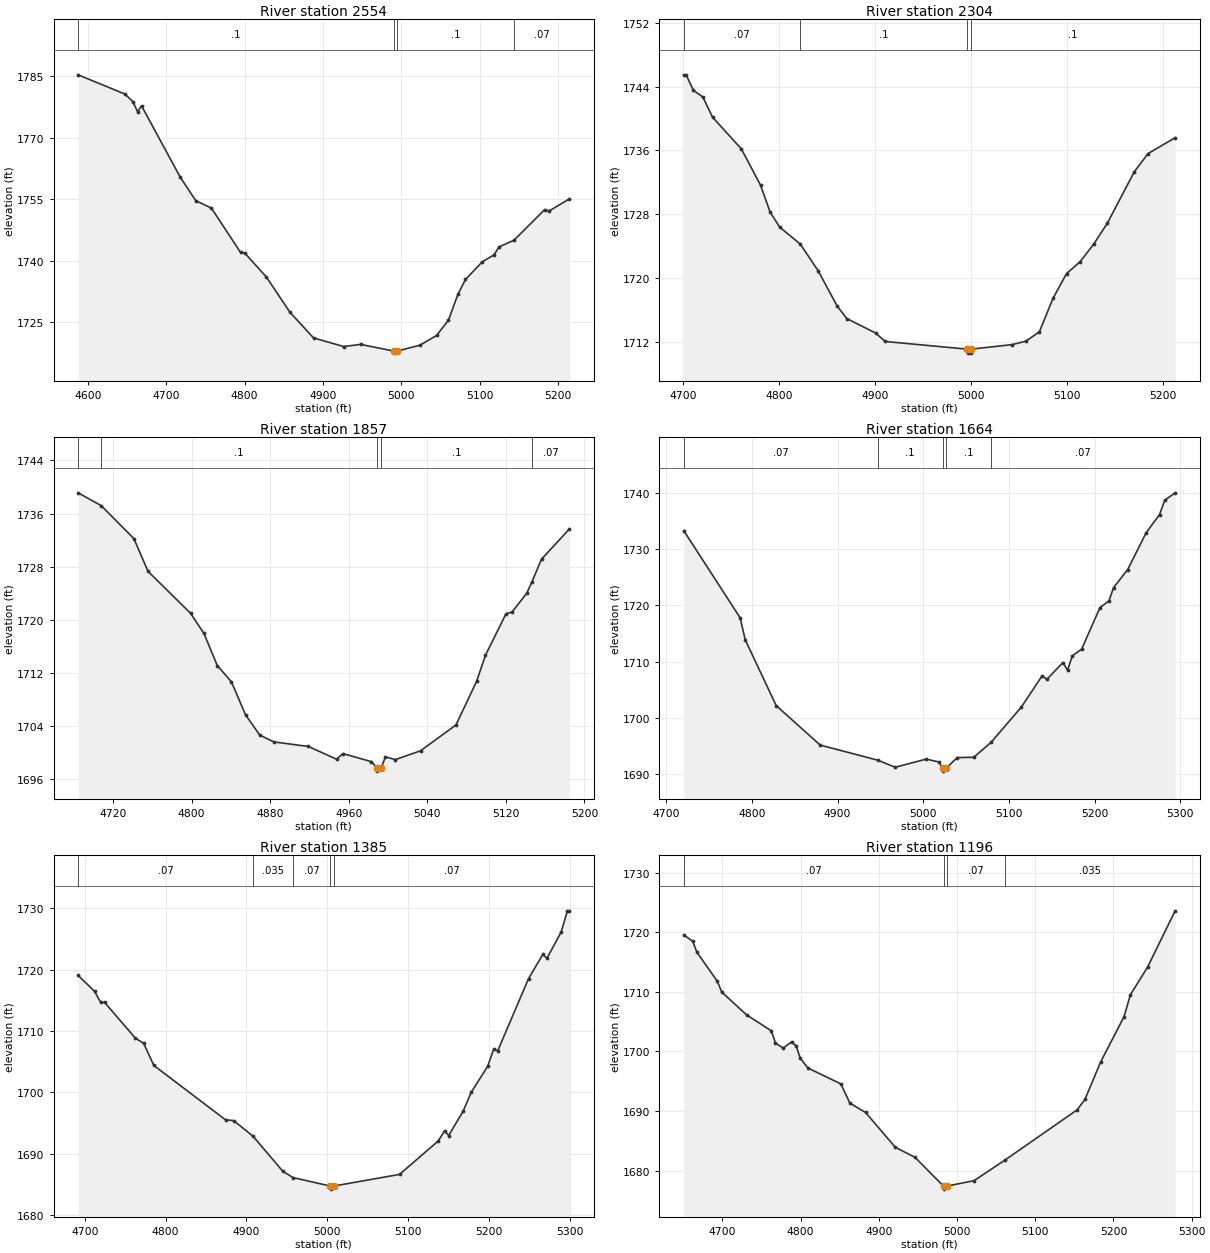
Type RM Length L Ch R = 1 ,2554    ,250,250,250
BEGIN DESCRIPTION:
Mapping XS 7b0c2df6
END DESCRIPTION:
XS GIS Cut Line= 3
       1962584.2     13912565.24      1962613.55     13912953.76
      1962817.56      13913076.1
#Sta/Elev= 30
  4587.4 1785.37  4647.3 1780.67  4657.4  1778.8  4663.4 1776.35  4668.4  1777.8
  4717.5 1760.51  4737.6 1754.66  4757.6 1752.86  4794.9 1742.01    4800 1741.92
  4827.8 1736.04  4857.9 1727.43    4888 1721.17  4926.5 1719.06  4948.2 1719.58
  4990.7 1717.95  4990.9 1717.45  4994.7 1717.95  5023.8 1719.37  5045.2 1721.76
  5060.3 1725.49  5072.4 1731.78  5082.1 1735.43  5103.5 1739.73  5118.6 1741.45
  5124.9 1743.38    5144    1745  5183.2 1752.48    5189 1752.15  5214.9 1755.11
#Mann= 4 ,-1 , 0
  4587.4      .1       0  4990.7     .05       0  4994.7      .1       0
    5144     .07       0
Bank Sta=4990.7,4994.7
XS Rating Curve= 0 ,0
Exp/Cntr=0.3,0.1

Type RM Length L Ch R = 1 ,2304    ,447,447,447
BEGIN DESCRIPTION:
Stream0048 5.0
END DESCRIPTION:
XS GIS Cut Line= 3
      1962124.97       13913075.        1962425.       13913075.
      1962575.03     13913225.03
#Sta/Elev= 30
  4700.3 1745.48  4702.8 1745.48  4710.3 1743.54  4720.3 1742.69  4730.3 1740.17
  4760.3  1736.2  4780.3 1731.65  4790.3 1728.28  4800.3 1726.38  4821.7 1724.27
  4840.3 1720.93  4860.3 1716.47  4870.3 1714.92  4900.3 1713.11  4910.3 1712.05
  4995.8 1711.09  4996.1 1710.59  4999.6 1710.59  4999.8 1711.09  5042.8 1711.66
  5056.9 1712.09    5071 1713.26  5085.2 1717.46  5099.3 1720.56  5113.5 1722.06
  5127.6 1724.25  5141.8 1726.87    5170 1733.34  5184.2  1735.6  5212.5  1737.6
#Mann= 4 ,-1 , 0
  4700.3     .07       0  4821.7      .1       0  4995.8     .05       0
  4999.8      .1       0
Bank Sta=4995.8,4999.8
XS Rating Curve= 0 ,0
Exp/Cntr=0.3,0.1

Type RM Length L Ch R = 1 ,1857    ,193,193,193
BEGIN DESCRIPTION:
Stream0048 4.0
END DESCRIPTION:
XS GIS Cut Line= 3
        1962075.       13913225.        1962275.       13913475.
      1962424.97     13913574.98
#Sta/Elev= 30
  4684.4 1739.12  4707.9 1737.19  4741.2 1732.21  4755.6 1727.27  4798.9 1720.94
  4812.5 1717.91  4826.1 1713.06  4840.5 1710.61  4854.9 1705.62  4869.3 1702.57
  4883.7 1701.53  4918.9 1700.84  4947.7 1698.91  4954.1 1699.77    4983 1698.55
    4989 1697.62  4989.2 1697.12    4993 1697.62  4997.4 1699.26  5007.6 1698.86
  5033.1 1700.19  5069.2 1704.09  5090.2 1710.66  5099.2  1714.6  5120.2 1720.89
  5126.2 1721.11  5141.3 1723.97  5146.6  1725.7  5156.3  1729.1  5184.8 1733.68
#Mann= 5 ,-1 , 0
  4684.4     .07       0  4707.9      .1       0    4989     .05       0
    4993      .1       0  5146.6     .07       0
Bank Sta=4989,4993
XS Rating Curve= 0 ,0
Exp/Cntr=0.3,0.1

Type RM Length L Ch R = 1 ,1664    ,279,279,279
BEGIN DESCRIPTION:
Mapping XS 16b084c2
END DESCRIPTION:
XS GIS Cut Line= 3
      1961934.85     13913474.11      1962218.34     13913659.27
      1962436.35     13913746.99
#Sta/Elev= 30
  4720.4 1733.31  4786.2  1717.8  4792.2 1713.87  4828.3 1702.17  4879.6 1695.14
  4946.9 1692.45  4967.2 1691.19  5003.4 1692.64  5018.5 1692.12  5022.5    1691
  5022.7  1690.5  5026.5    1691  5039.6 1692.91    5059 1692.97  5079.3 1695.65
  5114.6 1701.93  5138.8 1707.49  5144.2 1706.82    5163 1709.84  5168.4 1708.45
    5174 1711.04  5184.8  1712.2  5206.3 1719.63  5216.7 1720.79  5222.1 1723.17
  5238.6 1726.39  5260.2 1732.95  5275.8 1736.18  5281.8 1738.72    5294 1740.05
#Mann= 5 ,-1 , 0
  4720.4     .07       0  4946.9      .1       0  5022.5     .05       0
  5026.5      .1       0  5079.3     .07       0
Bank Sta=5022.5,5026.5
XS Rating Curve= 0 ,0
Exp/Cntr=0.3,0.1

Type RM Length L Ch R = 1 ,1385    ,189,189,189
BEGIN DESCRIPTION:
Stream0048 3.0
END DESCRIPTION:
XS GIS Cut Line= 3
      1961775.02       13913825.        1962075.       13913875.
      1962375.04     13913925.01
#Sta/Elev= 30
  4691.6 1719.07  4711.9 1716.49  4719.5 1714.68  4724.5 1714.66  4762.5 1708.84
  4772.7    1708  4785.4 1704.39  4874.1 1695.53  4884.2  1695.4  4908.2 1692.85
    4945 1687.14  4957.7 1686.11  5003.9 1684.73  5004.1 1684.23  5007.9 1684.73
  5089.5 1686.63  5137.6  1692.1  5145.3 1693.75  5150.3 1692.97  5168.1 1696.89
  5178.2    1700  5198.5 1704.23  5206.1 1707.07  5211.1 1706.79  5249.2 1718.55
  5266.9  1722.5    5272 1721.86  5289.7 1726.16  5297.3  1729.6  5299.9  1729.6
#Mann= 5 ,-1 , 0
  4691.6     .07       0  4908.2    .035       0  4957.7     .07       0
  5003.9     .05       0  5007.9     .07       0
Bank Sta=5003.9,5007.9
XS Rating Curve= 0 ,0
Exp/Cntr=0.3,0.1

Type RM Length L Ch R = 1 ,1196    ,84,84,84
BEGIN DESCRIPTION:
Mapping XS ff6949f9
END DESCRIPTION:
XS GIS Cut Line= 3
      1961714.19     13913944.68      1962129.63      13914081.9
      1962320.18      13914093.2
#Sta/Elev= 30
  4650.5 1719.55  4661.9 1718.49  4667.3 1716.65  4693.5 1711.77    4699 1709.98
  4730.8 1706.15  4762.5 1703.47  4767.8 1701.41  4777.7 1700.58  4788.3  1701.6
  4794.3 1700.94  4799.5 1698.86  4809.3 1697.23  4851.4 1694.56    4863 1691.33
    4883 1689.77  4921.2 1683.91  4946.2 1682.25  4982.7 1677.41  4982.9 1676.91
  4986.7 1677.41  5021.7 1678.33  5060.9 1681.75  5153.5  1690.2  5163.5 1691.95
  5183.5 1698.21  5213.6 1705.86  5221.7 1709.52  5243.7 1714.17  5278.9  1723.6
#Mann= 4 ,-1 , 0
  4650.5     .07       0  4982.7     .05       0  4986.7     .07       0
  5060.9    .035       0
Bank Sta=4982.7,4986.7
XS Rating Curve= 0 ,0
Exp/Cntr=0.3,0.1

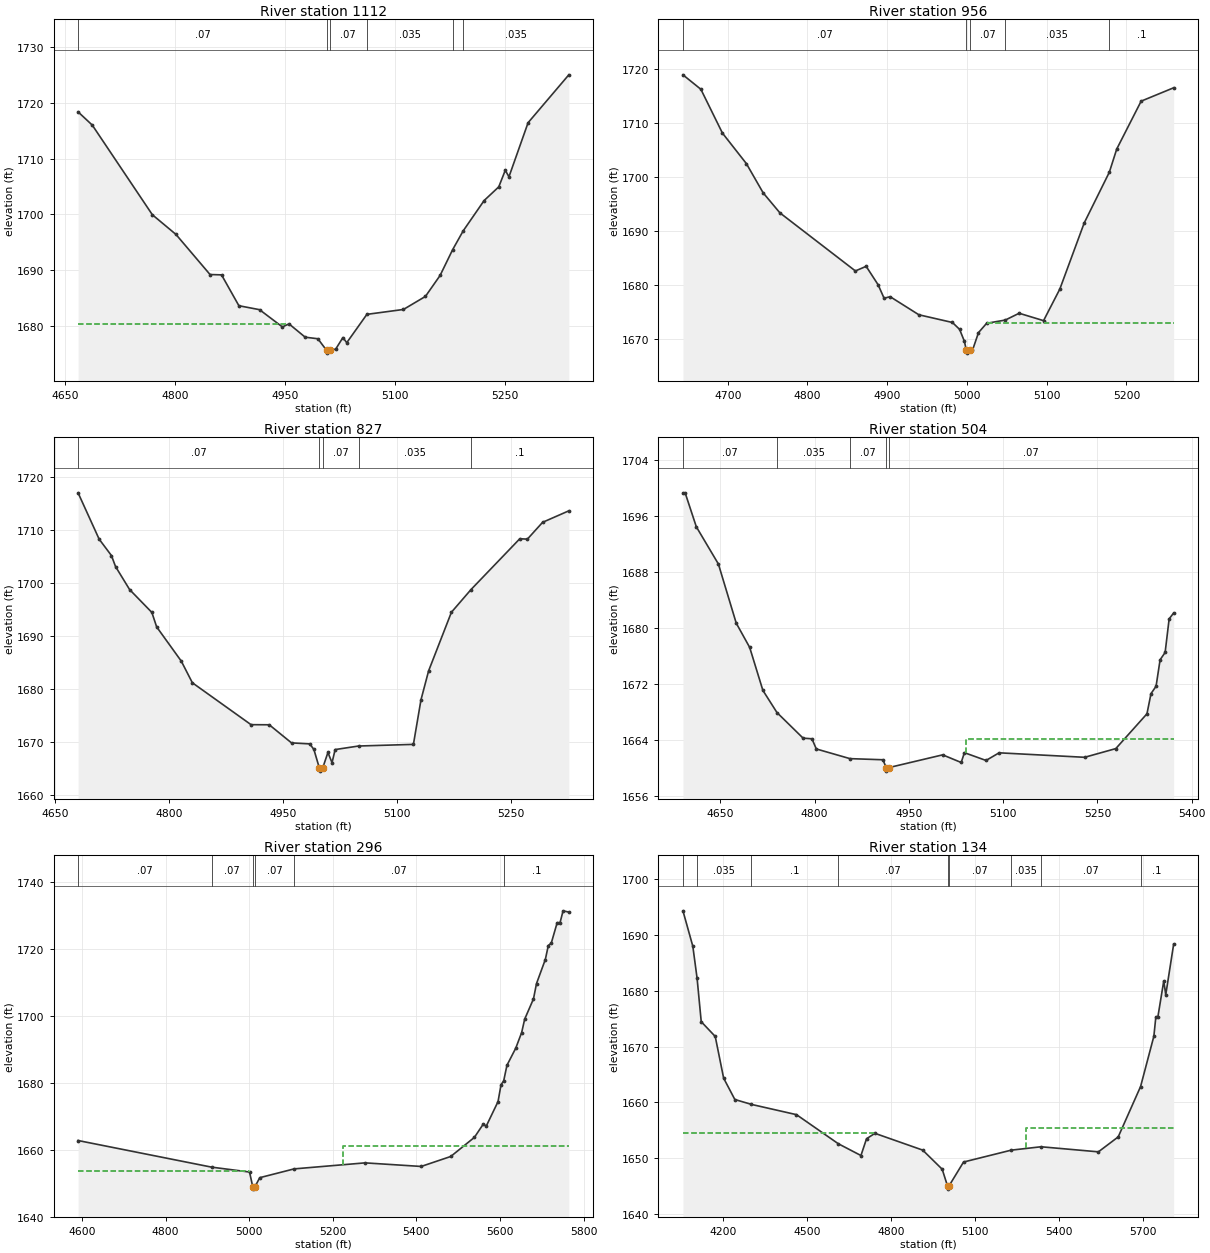
Type RM Length L Ch R = 1 ,1112    ,156,156,156
BEGIN DESCRIPTION:
Mapping XS 67abfe61
END DESCRIPTION:
XS GIS Cut Line= 3
      1961696.35     13914041.68      1962101.54     13914154.58
      1962350.58     13914162.69
#Sta/Elev= 30
  4667.6  1718.4    4687 1716.02    4769 1699.93  4801.2  1696.4  4847.7  1689.2
  4863.4 1689.14  4887.1  1683.6  4915.3 1682.89  4946.5 1679.79  4955.5 1680.34
  4977.6 1677.95  4994.9 1677.67  5006.8 1675.59    5007 1675.09  5010.8 1675.59
  5019.2 1675.81  5029.1 1677.89  5034.3 1676.96  5061.8 1682.05  5111.7 1682.93
  5141.7 1685.27  5161.7 1689.03  5178.8 1693.65  5193.2 1697.03  5221.8 1702.48
  5241.8 1704.94  5250.7 1707.92  5255.7 1706.74  5281.8 1716.45  5337.4 1725.05
#Mann= 6 ,-1 , 0
  4667.6     .07       0  5006.8     .05       0  5010.8     .07       0
  5061.8    .035       0  5178.8      .1       0  5193.2    .035       0
#XS Ineff= 2 , 0
         4955.35 1680.38
Permanent Ineff=
       F       F
Bank Sta=5006.8,5010.8
XS Rating Curve= 0 ,0
Exp/Cntr=0.3,0.1

Type RM Length L Ch R = 1 ,956     ,129,129,129
BEGIN DESCRIPTION:
Stream0048 2.0
END DESCRIPTION:
XS GIS Cut Line= 3
      1961675.04     13914075.03        1961975.       13914275.
      1962225.04     13914325.01
#Sta/Elev= 30
  4643.8 1718.92  4666.3 1716.24  4693.3 1708.13  4723.4 1702.46  4744.4 1697.05
  4765.4 1693.34  4860.1 1682.57  4873.6 1683.43  4888.6 1680.01  4896.1 1677.51
  4903.7  1677.8  4939.7 1674.45  4981.8 1673.02  4990.8 1671.74  4996.8 1669.54
  4999.3 1667.84  4999.6 1667.34  5003.3 1667.84  5006.9 1667.84  5014.5 1671.14
  5024.7 1672.87  5048.1 1673.47  5065.5 1674.73  5096.1 1673.36  5116.5 1679.21
  5147.1 1691.47  5178.6 1700.87  5187.9 1705.17  5218.5 1714.04  5259.3 1716.52
#Mann= 5 ,-1 , 0
  4643.8     .07       0  4999.3     .05       0  5003.3     .07       0
  5048.1    .035       0  5178.6      .1       0
#XS Ineff= 2 , 0
                         5024.84         1672.96
Permanent Ineff=
       F       F
Bank Sta=4999.3,5003.3
XS Rating Curve= 0 ,0
Exp/Cntr=0.3,0.1

Type RM Length L Ch R = 1 ,827     ,323,323,323
BEGIN DESCRIPTION:
Mapping XS aeec900c
END DESCRIPTION:
XS GIS Cut Line= 3
      1961629.43      13914263.3      1961944.35      13914393.1
      1962249.49     13914398.02
#Sta/Elev= 30
  4680.2 1717.05  4707.9 1708.31  4724.1 1705.21  4729.5 1703.13    4748 1698.79
  4777.3 1694.47  4783.6 1691.74    4816 1685.28  4830.6 1681.19  4907.8 1673.28
  4931.8 1673.26  4961.1 1669.84  4985.1 1669.65  4990.5 1668.61  4997.9 1665.01
  4998.1 1664.51  5001.9 1665.01    5009 1668.03  5014.4  1666.1  5018.5 1668.58
  5049.3 1669.25  5121.5 1669.56  5131.5    1678  5141.5 1683.44  5171.5  1694.5
  5197.3 1698.79  5261.5 1708.38  5271.5 1708.31  5291.5 1711.48    5326 1713.65
#Mann= 5 ,-1 , 0
  4680.2     .07       0  4997.9     .05       0  5001.9     .07       0
  5049.3    .035       0  5197.3      .1       0
Bank Sta=4997.9,5001.9
XS Rating Curve= 0 ,0
Exp/Cntr=0.3,0.1

Type RM Length L Ch R = 1 ,504     ,208,208,208
BEGIN DESCRIPTION:
Stream0048 1.0
END DESCRIPTION:
XS GIS Cut Line= 4
      1961624.99     13914424.99      1961871.02      13914685.7
      1961988.15     13914664.58      1962225.03     13914474.98
#Sta/Elev= 30
  4590.5 1699.26    4594 1699.26  4611.8 1694.42  4646.9 1689.12  4675.3 1680.69
  4696.7 1677.23  4717.7 1671.11  4740.1 1667.95  4781.7  1664.3  4795.8 1664.21
  4802.7 1662.76  4856.3 1661.38  4908.7 1661.22    4914  1660.1  4914.2  1659.6
    4918  1660.1  5003.8 1661.92  5033.3 1660.83  5038.4 1662.23  5072.8 1661.12
  5093.6 1662.21  5229.7 1661.57  5279.3 1662.81  5328.9 1667.77  5335.3 1670.64
  5343.4  1671.7  5349.8 1675.47  5357.8 1676.51  5364.2  1681.3  5371.4 1682.14
#Mann= 5 ,-1 , 0
  4590.5     .07       0  4740.1    .035       0  4856.3     .07       0
    4914     .05       0    4918     .07       0
#XS Ineff= 2 , 0
                         5040.36         1664.17
Permanent Ineff=
       F       F
Bank Sta=4914,4918
XS Rating Curve= 0 ,0
Exp/Cntr=0.3,0.1

Type RM Length L Ch R = 1 ,296     ,162,162,162
BEGIN DESCRIPTION:
Stream0048 0.0
END DESCRIPTION:
XS GIS Cut Line= 4
      1961557.78     13914741.49      1961872.63     13914888.63
      1962070.38     13914868.77      1962509.48     13914420.05
#Sta/Elev= 30
  4590.6 1662.78  4910.2 1654.82  5000.8 1653.36  5008.9 1648.75  5009.1 1648.25
  5012.9 1648.75  5025.2 1651.67  5107.5  1654.3  5277.2  1656.1  5411.5 1655.03
  5482.2 1658.01  5538.8 1663.72  5560.1  1667.7  5567.1 1667.07  5595.4 1674.43
  5602.5 1679.45  5608.9 1680.62  5616.7 1685.27  5637.8  1690.4  5651.9 1695.07
  5659.1 1699.06  5680.2 1705.14  5687.4  1709.7  5708.5 1716.89  5715.7 1721.08
  5722.7 1721.78  5736.8 1727.89  5743.8 1727.94    5751 1731.45  5764.7 1731.07
#Mann= 6 ,-1 , 0
  4590.6     .07       0  4910.2     .07       0  5008.9     .05       0
  5012.9     .07       0  5107.5     .07       0  5608.9      .1       0
#XS Ineff= 2 , 0
         5000.46 1653.55 5225.17         1661.16
Permanent Ineff=
       F       F
Bank Sta=5008.9,5012.9
XS Rating Curve= 0 ,0
Exp/Cntr=0.3,0.1

Type RM Length L Ch R = 1 ,134     ,0,0,0
BEGIN DESCRIPTION:
Stream0048 0.5
END DESCRIPTION:
XS GIS Cut Line= 4
      1961049.74     13915072.31      1961816.85     13915091.15
       1962175.1     13914956.33      1962600.56     13914530.61
#Sta/Elev= 30
  4056.7 1694.35    4092 1687.99  4107.3 1682.22    4122 1674.46    4172 1671.81
    4202 1664.33    4242  1660.5  4301.4 1659.62  4462.1 1657.78  4611.5 1652.56
  4692.2 1650.45  4712.2 1653.46  4742.2 1654.43  4912.7 1651.42  4982.3 1647.99
  5001.7 1644.92    5002 1644.42  5005.7 1644.92  5058.5 1649.28  5228.5 1651.41
    5335 1652.02    5540 1651.11  5610.7 1653.79  5690.6 1662.83    5738 1671.85
  5745.1 1675.35  5752.2 1675.28  5773.4  1681.8  5780.4 1679.28  5808.7 1688.39
#Mann= 9 ,-1 , 0
  4056.7     .07       0  4107.3    .035       0  4301.4      .1       0
  4611.5     .07       0  5001.7     .05       0  5005.7     .07       0
  5228.5    .035       0    5335     .07       0  5690.6      .1       0
#XS Ineff= 2 , 0
         4737.26 1654.49 5280.72         1655.33
Permanent Ineff=
       F       F
Bank Sta=5001.7,5005.7
XS Rating Curve= 0 ,0
Exp/Cntr=0.3,0.1

Chan Stop Cuts=-1
Use User Specified Reach Order=0
Composite Channel Slope=5