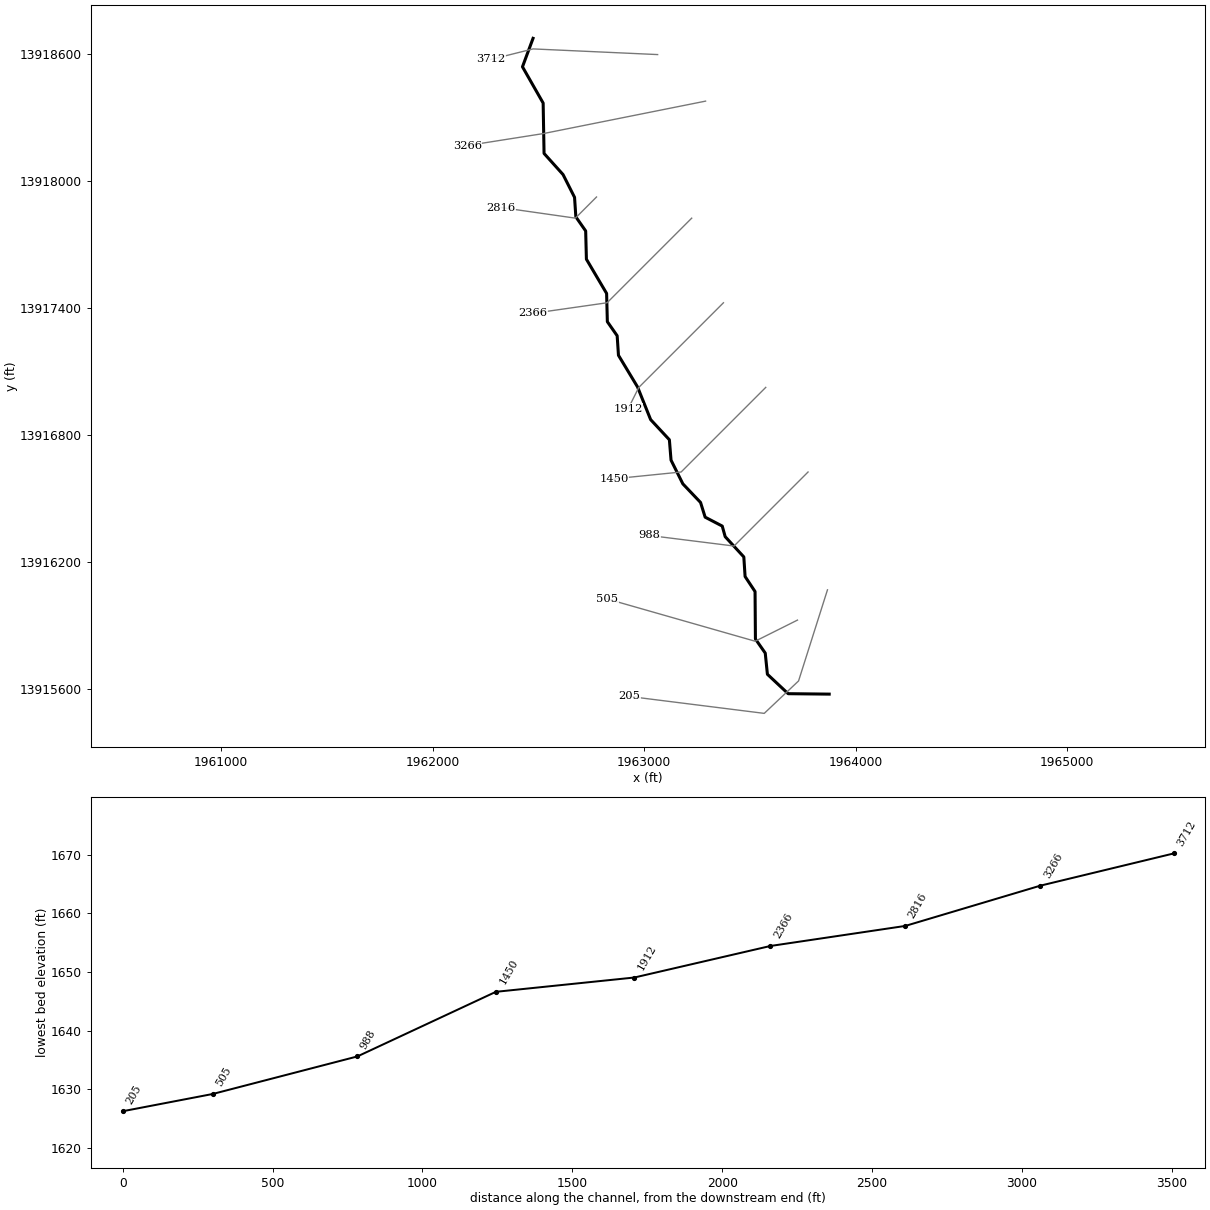
--- Stream0049.prj (project) ---

Proj Title=Stream0049 Base Level Engineering
Current Plan=p01
Default Exp/Contr=0.3,0.1
English Units
Geom File=g01
Flow File=f01
Plan File=p01
BEGIN DESCRIPTION:
Stream0049
END DESCRIPTION:

--- Stream0049.p01 (plan) ---

Plan Title=Multiple Run
Short Identifier=Multiple
Geom File=g01
Flow File=f01
Subcritical Flow
K Sum by GR= 0
Std Step Tol= 0.01
Critical Tol= 0.01
Num of Std Step Trials= 20
Max Error Tol= 0.3
Flow Tol Ratio= 0.001
Split Flow NTrial= 30
Split Flow Tol= 0.02
Split Flow Ratio= 0.02
Log Output Level= 0
Friction Slope Method= 1
Unsteady Friction Slope Method= 2
Unsteady Bridges Friction Slope Method= 1
Parabolic Critical Depth
Global Vel Dist=  1 , 1 , 1
Global Log Level= 0
CheckData=True
Encroach Param= -1, 0, 0, 0
BEGIN DESCRIPTION:
Multiple Run
END DESCRIPTION:

--- Stream0049.f01 (steady flow) ---

Flow Title=Multiple
Number of Profiles=7
Profile Names=10-year,25-year,50-year,1pct_min,100-year,1pct_plu,500-year
River Rch & RM= Stream0049,Reach-1,3712
    2021    3552    5052    3468    6920   13808   12826
Boundary for River Rch & Prof#=Stream0049,Reach-1,1
Up Type=0
Dn Type=3
Dn Slope=0.005
Boundary for River Rch & Prof#=Stream0049,Reach-1,2
Up Type=0
Dn Type=3
Dn Slope=0.005
Boundary for River Rch & Prof#=Stream0049,Reach-1,3
Up Type=0
Dn Type=3
Dn Slope=0.005
Boundary for River Rch & Prof#=Stream0049,Reach-1,4
Up Type=0
Dn Type=3
Dn Slope=0.005
Boundary for River Rch & Prof#=Stream0049,Reach-1,5
Up Type=0
Dn Type=3
Dn Slope=0.005
Boundary for River Rch & Prof#=Stream0049,Reach-1,6
Up Type=0
Dn Type=3
Dn Slope=0.005
Boundary for River Rch & Prof#=Stream0049,Reach-1,7
Up Type=0
Dn Type=3
Dn Slope=0.005

--- Stream0049.g01 (geometry) ---

Geom Title=Existing Conditions

River Reach=Stream0049,Reach-1
Reach XY= 30
      1962475.00     13918675.00      1962425.03     13918540.38
      1962522.76     13918369.07      1962527.06     13918130.86
      1962616.84     13918031.05      1962671.17     13917923.42
      1962677.36     13917830.98      1962723.77     13917764.49
      1962727.25     13917630.93      1962822.75     13917469.07
      1962826.23     13917335.51      1962872.64     13917269.02
      1962878.83     13917176.58      1962968.92     13917027.20
      1963030.85     13916872.71      1963119.46     13916777.42
      1963127.33     13916680.97      1963183.16     13916568.95
      1963266.82     13916481.02      1963288.55     13916411.47
      1963369.35     13916369.37      1963383.30     13916319.26
      1963471.38     13916223.50      1963477.36     13916130.98
      1963524.48     13916059.78      1963526.22     13915835.50
      1963572.64     13915769.02      1963582.85     13915668.81
      1963680.84     13915577.04      1963875.00     13915575.00

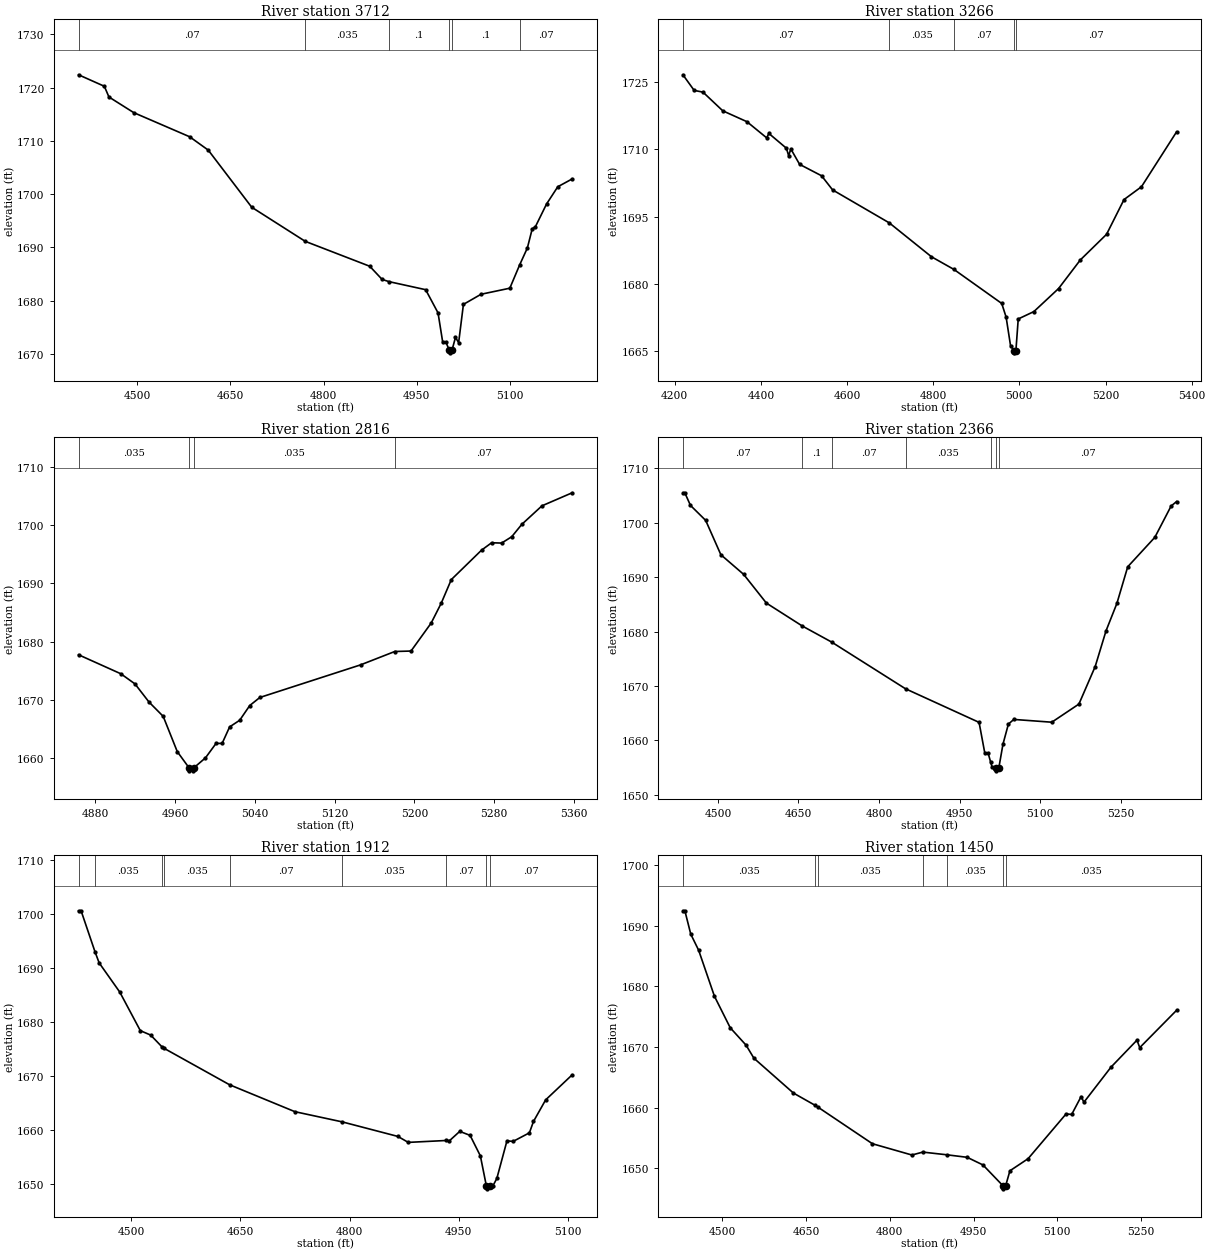
Type RM Length L Ch R = 1,3712,446,446,446
BEGIN DESCRIPTION:
Stream0049 8.0
END DESCRIPTION:
XS GIS Cut Line= 3
      1963063.91     13918598.22      1962475.00     13918625.00
      1962274.98     13918574.99
#Sta/Elev= 30
  4405.1 1722.43  4446.7 1720.27  4454.1 1718.26  4494.1 1715.32  4584.2 1710.79
  4614.2 1708.28  4684.3 1697.55  4770.5 1691.15  4874.5 1686.47  4894.5 1683.99
  4906.0 1683.57  4964.6 1682.07  4984.6 1677.71  4992.1 1672.22  4997.2 1672.22
  5002.8 1670.71  5003.1 1670.21  5007.1 1670.71  5012.7 1673.11  5017.8 1672.13
  5025.5 1679.31  5053.9 1681.21  5100.3 1682.35  5116.2 1686.74  5128.6 1689.91
  5136.4 1693.50  5141.5 1693.89  5159.5 1698.16  5177.6 1701.40  5200.8 1702.87
#Mann=6,-1,0
  4405.1    0.07       0  4770.5   0.035       0  4906.0     0.1       0
  5002.8    0.05       0  5007.1     0.1       0  5116.2    0.07       0
Bank Sta=5002.8,5007.1
Exp/Cntr=0.3,0.1

Type RM Length L Ch R = 1,3266,450,450,450
BEGIN DESCRIPTION:
Stream0049 7.0
END DESCRIPTION:
XS GIS Cut Line= 3
      1963290.55     13918378.17      1962525.00     13918225.00
      1962164.57     13918168.20
#Sta/Elev= 30
  4219.2 1726.51  4245.3 1723.04  4265.8 1722.65  4311.7 1718.50  4367.8 1716.08
  4413.6 1712.49  4418.7 1713.47  4459.4 1710.18  4464.6 1708.52  4469.7 1710.02
  4490.0 1706.60  4541.0 1704.06  4566.6 1700.92  4698.3 1693.58  4796.0 1686.06
  4848.2 1683.24  4959.1 1675.68  4969.3 1672.64  4979.5 1666.33  4987.5 1665.20
  4987.8 1664.70  4992.0 1665.20  4997.4 1672.23  5033.7 1673.87  5091.0 1678.99
  5141.6 1685.36  5202.4 1691.05  5242.9 1698.77  5283.4 1701.62  5364.8 1713.81
#Mann=5,-1,0
  4219.2    0.07       0  4698.3   0.035       0  4848.2    0.07       0
  4987.5    0.05       0  4992.0    0.07       0
Bank Sta=4987.5,4992
Exp/Cntr=0.3,0.1

Type RM Length L Ch R = 1,2816,450,450,450
BEGIN DESCRIPTION:
Stream0049 6.0
END DESCRIPTION:
XS GIS Cut Line= 3
      1962775.01     13917925.01      1962675.00     13917825.00
      1962324.99     13917875.00
#Sta/Elev= 30
  4863.2 1677.76  4905.6 1674.50  4919.8 1672.76  4933.9 1669.64  4948.1 1667.19
  4962.2 1661.14  4974.1 1658.34  4974.4 1657.84  4978.3 1657.84  4978.7 1658.34
  4990.5 1660.07  5001.1 1662.55  5007.2 1662.55  5014.7 1665.38  5024.8 1666.52
  5034.9 1669.05  5045.0 1670.43  5146.1 1676.03  5180.3 1678.32  5196.6 1678.40
  5216.8 1683.20  5226.9 1686.61  5237.0 1690.66  5267.3 1695.71  5277.4 1696.98
  5287.5 1696.93  5297.6 1698.02  5307.7 1700.14  5327.9 1703.32  5358.2 1705.56
#Mann=4,-1,0
  4863.2   0.035       0  4974.1   0.035       0  4978.7   0.035       0
  5180.3    0.07       0
Bank Sta=4974.1,4978.7
Exp/Cntr=0.3,0.1

Type RM Length L Ch R = 1,2366,454,454,454
BEGIN DESCRIPTION:
Stream0049 5.0
END DESCRIPTION:
XS GIS Cut Line= 3
      1963224.98     13917824.98      1962825.00     13917425.00
      1962475.00     13917375.00
#Sta/Elev= 30
  4434.8 1705.48  4438.3 1705.48  4448.9 1703.16  4477.2 1700.41  4505.5 1694.10
  4547.9 1690.50  4590.3 1685.22  4657.2 1681.01  4711.7 1678.07  4849.3 1669.49
  4986.3 1663.32  4996.9 1657.71  5003.0 1657.71  5007.8 1656.05  5010.6 1655.08
  5018.4 1654.92  5018.7 1654.42  5023.0 1654.92  5030.8 1659.32  5040.9 1663.01
  5051.0 1663.86  5121.7 1663.35  5172.2 1666.68  5202.5 1673.57  5222.7 1680.13
  5242.9 1685.16  5263.1 1691.89  5313.6 1697.30  5343.9 1703.05  5354.0 1703.86
#Mann=7,-1,0
  4434.8    0.07       0  4657.2     0.1       0  4711.7    0.07       0
  4849.3   0.035       0  5007.8    0.07       0  5018.4   0.035       0
  5023.0    0.07       0
Bank Sta=5018.4,5023
Exp/Cntr=0.3,0.1

Type RM Length L Ch R = 1,1912,462,462,462
BEGIN DESCRIPTION:
Stream0049 4.0
END DESCRIPTION:
XS GIS Cut Line= 3
      1963374.99     13917424.99      1962975.00     13917025.00
      1962924.99     13916924.98
#Sta/Elev= 30
  4428.0 1700.58  4431.5 1700.58  4450.6 1692.98  4456.3 1690.92  4484.6 1685.51
  4512.8 1678.36  4527.0 1677.54  4542.5 1675.36  4544.8 1675.13  4635.3 1668.33
  4725.0 1663.34  4789.9 1661.45  4866.4 1658.75  4880.5 1657.65  4932.3 1658.00
  4937.1 1657.96  4951.2 1659.69  4965.4 1658.95  4979.5 1655.15  4987.8 1649.54
  4988.1 1649.04  4992.5 1649.54  4996.5 1649.54  5002.1 1650.96  5016.0 1657.94
  5024.4 1657.83  5046.8 1659.42  5052.4 1661.53  5069.1 1665.53  5105.5 1670.17
#Mann=9,-1,0
  4428.0    0.07       0  4450.6   0.035       0  4542.5     0.1       0
  4544.8   0.035       0  4635.3    0.07       0  4789.9   0.035       0
  4932.3    0.07       0  4987.8    0.05       0  4992.5    0.07       0
Bank Sta=4987.8,4992.5
Exp/Cntr=0.3,0.1

Type RM Length L Ch R = 1,1450,462,462,462
BEGIN DESCRIPTION:
Stream0049 3.0
END DESCRIPTION:
XS GIS Cut Line= 3
      1963574.97     13917024.97      1963175.00     13916625.00
      1962858.15     13916593.00
#Sta/Elev= 30
  4429.5 1692.46  4433.0 1692.46  4443.6 1688.60  4457.7 1685.95  4486.0 1678.36
  4514.3 1673.16  4542.6 1670.30  4556.7 1668.14  4627.4 1662.40  4665.6 1660.41
  4671.1 1660.09  4768.9 1654.04  4839.6 1652.18  4859.2 1652.66  4901.7 1652.22
  4938.6 1651.80  4966.9 1650.54  5002.8 1647.10  5003.2 1646.60  5007.5 1647.10
  5015.2 1649.58  5047.7 1651.57  5115.8 1658.96  5125.8 1658.87  5142.7 1661.82
  5147.7 1660.88  5196.2 1666.67  5242.7 1671.12  5247.7 1669.89  5313.6 1676.04
#Mann=7,-1,0
  4429.5   0.035       0  4665.6    0.07       0  4671.1   0.035       0
  4859.2    0.07       0  4901.7   0.035       0  5002.8   0.035       0
  5007.5   0.035       0
Bank Sta=5002.8,5007.5
Exp/Cntr=0.3,0.1

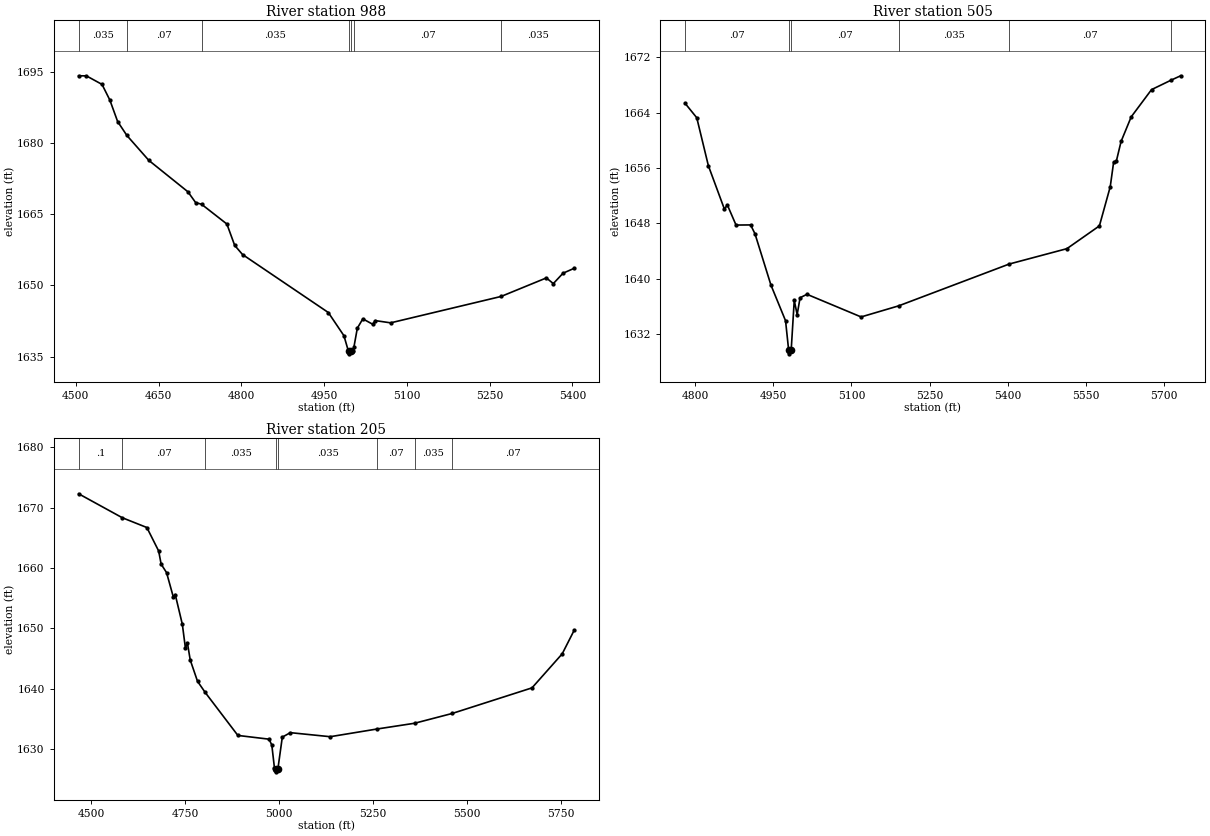
Type RM Length L Ch R = 1,988,483,483,483
BEGIN DESCRIPTION:
Stream0049 2.0
END DESCRIPTION:
XS GIS Cut Line= 3
      1963775.00     13916625.00      1963425.00     13916275.00
      1963024.99     13916325.00
#Sta/Elev= 30
  4505.1 1694.25  4519.2 1694.23  4547.5 1692.43  4561.7 1689.12  4575.8 1684.59
  4592.6 1681.65  4632.4 1676.39  4703.1 1669.78  4717.2 1667.49  4727.9 1667.14
  4773.8 1662.97  4787.9 1658.47  4802.1 1656.54  4957.6 1644.30  4985.9 1639.41
  4994.2 1636.08  4994.5 1635.58  4998.9 1636.08  5002.6 1636.08  5004.1 1637.05
  5010.2 1641.00  5020.2 1642.96  5037.9 1641.83  5042.9 1642.59  5070.6 1642.12
  5270.8 1647.69  5352.8 1651.60  5365.4 1650.40  5383.0 1652.59  5403.2 1653.63
#Mann=7,-1,0
  4505.1   0.035       0  4592.6    0.07       0  4727.9   0.035       0
  4994.2   0.035       0  4998.9   0.035       0  5004.1    0.07       0
  5270.8   0.035       0
Bank Sta=4994.2,4998.9
Exp/Cntr=0.3,0.1

Type RM Length L Ch R = 1,505,300,300,300
BEGIN DESCRIPTION:
Stream0049 1.0
END DESCRIPTION:
XS GIS Cut Line= 3
      1963725.01     13915925.00      1963525.00     13915825.00
      1962825.03     13916024.99
#Sta/Elev= 30
  4780.5 1665.35  4802.9 1663.27  4825.2 1656.34  4856.0 1650.07  4861.6 1650.68
  4878.3 1647.77  4906.3 1647.79  4914.7 1646.51  4945.4 1639.09  4973.4 1633.95
  4979.4 1629.67  4979.7 1629.17  4984.2 1629.67  4990.1 1636.89  4995.7 1634.84
  5001.3 1637.27  5014.5 1637.77  5118.5 1634.50  5190.6 1636.10  5402.9 1642.14
  5513.7 1644.36  5576.1 1647.65  5596.9 1653.30  5603.4 1656.84  5608.6 1656.99
  5617.7 1659.84  5637.2 1663.40  5676.2 1667.33  5713.3 1668.68  5732.1 1669.33
#Mann=6,-1,0
  4780.5    0.07       0  4979.4    0.05       0  4984.2    0.07       0
  5190.6   0.035       0  5402.9    0.07       0  5713.3   0.035       0
Bank Sta=4979.4,4984.2
Exp/Cntr=0.3,0.1

Type RM Length L Ch R = 1,205,0,0,0
BEGIN DESCRIPTION:
Stream0049 0.0
END DESCRIPTION:
XS GIS Cut Line= 4
      1963866.80     13916067.97      1963730.15     13915637.33
      1963567.90     13915483.98      1962929.76     13915564.12
#Sta/Elev= 30
  4466.8 1672.29  4583.0 1668.32  4648.3 1666.70  4679.7 1662.81  4686.3 1660.63
  4700.7 1659.23  4718.6 1655.21  4723.8 1655.60  4742.7 1650.66  4750.9 1646.71
  4756.1 1647.60  4763.7 1644.75  4783.1 1641.22  4803.5 1639.38  4890.4 1632.26
  4973.4 1631.64  4980.7 1630.66  4987.6 1626.92  4992.1 1626.73  4992.4 1626.23
  4996.9 1626.73  5008.6 1631.98  5030.0 1632.72  5136.0 1632.05  5261.0 1633.33
  5360.7 1634.28  5460.5 1635.90  5672.8 1640.14  5753.2 1645.78  5785.0 1649.68
#Mann=8,-1,0
  4466.8     0.1       0  4583.0    0.07       0  4803.5   0.035       0
  4992.1   0.035       0  4996.9   0.035       0  5261.0    0.07       0
  5360.7   0.035       0  5460.5    0.07       0
Bank Sta=4992.1,4996.9
Exp/Cntr=0.3,0.1

Chan Stop Cuts=-1