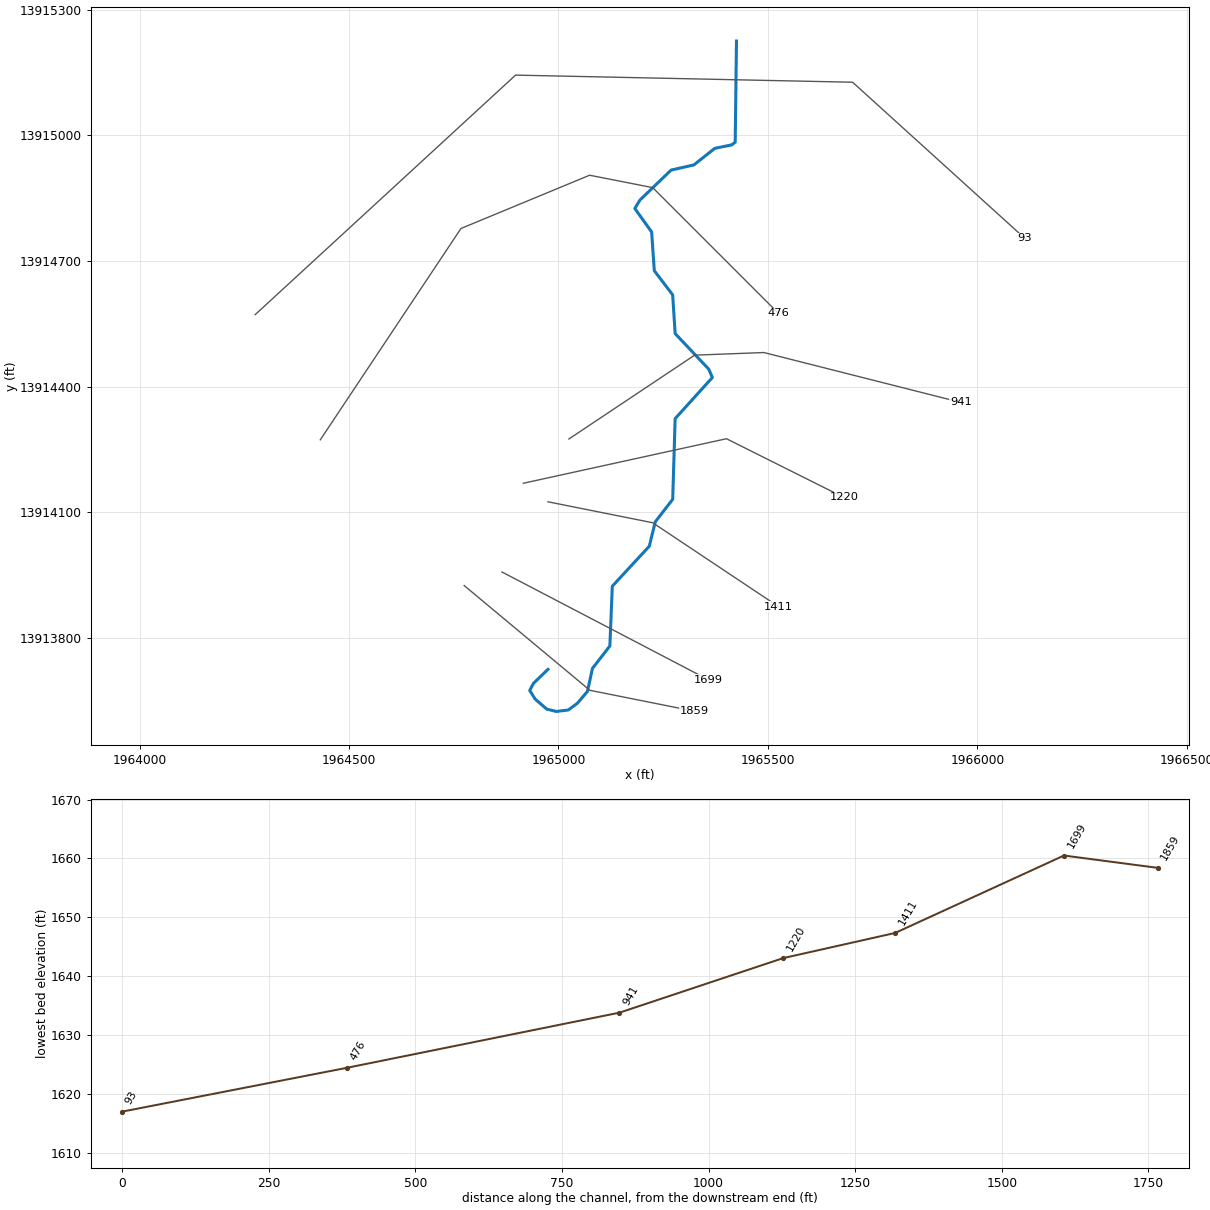
--- Stream0050.prj (project) ---

Proj Title=Stream0050 Base Level Engineering
Current Plan=p01
Default Exp/Contr=0.3,0.1
English Units
Geom File=g01
Flow File=f01
Plan File=p01
Y Axis Title=Elevation
X Axis Title(PF)=Main Channel Distance
X Axis Title(XS)=Station
BEGIN DESCRIPTION:
Stream0050
END DESCRIPTION:
DSS Export Rating Curves= 0
DSS Export Rating Curve Sorted= 0
DSS Export Volume Flow Curves= 0
DXF OffsetX= 0
DXF OffsetY= 0
DXF ScaleX= 1
DXF ScaleY= 10

--- Stream0050.p01 (plan) ---

Plan Title=Multiple Run
Short Identifier=Multiple
Geom File=g01
Flow File=f01
Subcritical Flow
K Sum by GR= 0
Std Step Tol= 0.01
Critical Tol= 0.01
Num of Std Step Trials= 20
Max Error Tol= 0.3
Flow Tol Ratio= 0.001
Split Flow NTrial= 30
Split Flow Tol= 0.02
Split Flow Ratio= 0.02
Log Output Level= 0
Friction Slope Method= 1
Unsteady Friction Slope Method= 2
Unsteady Bridges Friction Slope Method= 1
Parabolic Critical Depth
Global Vel Dist=  1 , 1 , 1
Global Log Level= 0
CheckData=True
Encroach Param= -1, 0, 0, 0
BEGIN DESCRIPTION:
Multiple Run
END DESCRIPTION:

--- Stream0050.f01 (steady flow) ---

Flow Title=Multiple
Number of Profiles=7
Profile Names=10-year,25-year,50-year,1pct_min,100-year,1pct_plu,500-year
River Rch & RM= Stream0050,Reach-1,1859
     664    1101    1508    1003    2001    3993    3470
Boundary for River Rch & Prof#=Stream0050,Reach-1,1
Up Type=0
Dn Type=3
Dn Slope=0.005
Boundary for River Rch & Prof#=Stream0050,Reach-1,2
Up Type=0
Dn Type=3
Dn Slope=0.005
Boundary for River Rch & Prof#=Stream0050,Reach-1,3
Up Type=0
Dn Type=3
Dn Slope=0.005
Boundary for River Rch & Prof#=Stream0050,Reach-1,4
Up Type=0
Dn Type=3
Dn Slope=0.005
Boundary for River Rch & Prof#=Stream0050,Reach-1,5
Up Type=0
Dn Type=3
Dn Slope=0.005
Boundary for River Rch & Prof#=Stream0050,Reach-1,6
Up Type=0
Dn Type=3
Dn Slope=0.005
Boundary for River Rch & Prof#=Stream0050,Reach-1,7
Up Type=0
Dn Type=3
Dn Slope=0.005

--- Stream0050.g01 (geometry) ---

Geom Title=Existing Conditions
Program Version=4.10

River Reach=Stream0050      ,Reach-1
Reach XY= 30
        1964975.       13913725.      1964940.33     13913691.61
      1964931.46     13913674.62      1964944.15     13913654.27
      1964972.24     13913629.97      1964995.04     13913624.47
      1965023.52       13913628.      1965045.46     13913644.26
      1965069.27     13913672.38      1965081.15     13913727.14
      1965122.75     13913780.93      1965128.55     13913923.53
      1965216.84     13914018.95      1965231.14     13914077.17
      1965272.76     13914130.93      1965278.56     13914323.54
      1965367.39     13914421.67      1965358.77     13914441.65
      1965278.64      13914526.5      1965272.64     13914619.02
      1965228.85      13914676.6      1965222.44     13914769.11
      1965182.31     13914825.11      1965194.27     13914845.07
      1965268.91     13914916.86      1965323.29     13914929.18
      1965373.21     13914968.73      1965413.33     13914976.94
      1965421.94     13914983.28        1965425.       13915225.

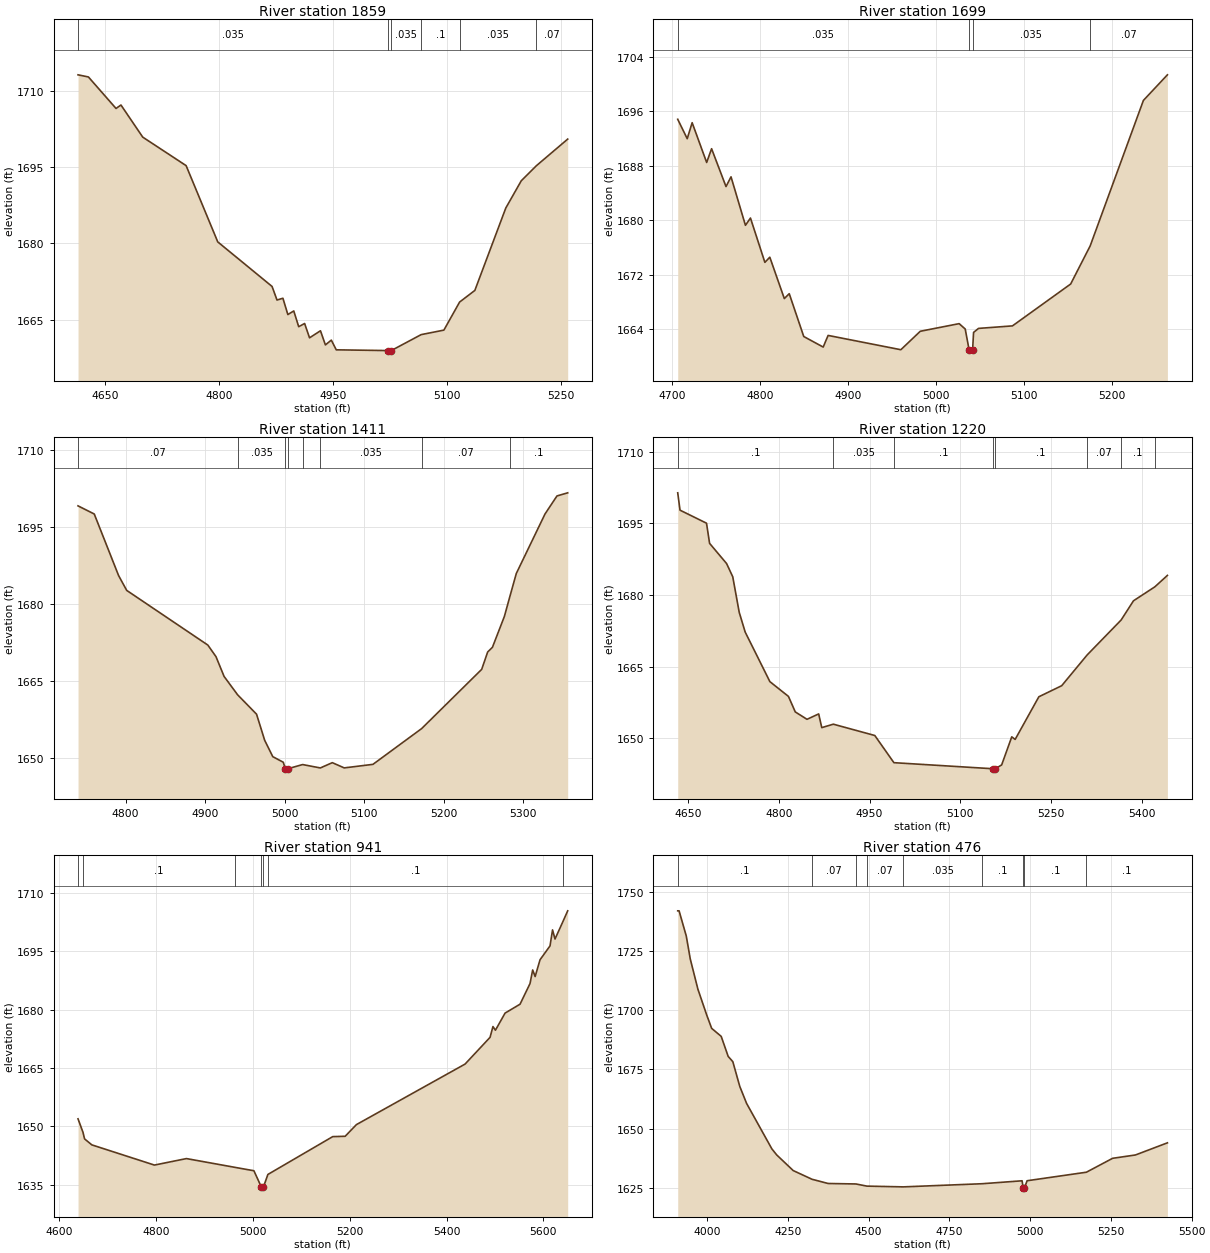
Type RM Length L Ch R = 1 ,1859    ,160,160,160
BEGIN DESCRIPTION:
Stream0050 4.0
END DESCRIPTION:
XS GIS Cut Line= 3
      1964775.01       13913925.        1965075.       13913675.
      1965325.04     13913624.99
#Sta/Elev= 30
  4613.9 1713.18  4627.6 1712.76    4664 1706.56  4670.5 1707.24  4699.2 1700.92
  4756.4 1695.31  4798.1  1680.3  4869.7 1671.53  4876.2 1668.86    4884 1669.21
  4890.5    1666  4898.3 1666.71  4904.8 1663.61  4912.6 1664.24  4919.1 1661.42
  4933.5 1662.81    4940 1660.03  4947.8 1660.97  4954.3 1659.06  5022.8 1658.91
  5023.1 1658.41  5026.8 1658.91  5066.2 1662.05  5096.2 1662.94  5116.9 1668.46
    5137 1670.75  5177.8 1686.97  5198.2 1692.33  5218.1 1695.29  5259.4 1700.53
#Mann= 6 ,-1 , 0
  4613.9    .035       0  5022.8    .035       0  5026.8    .035       0
  5066.2      .1       0  5116.9    .035       0  5218.1     .07       0
Bank Sta=5022.8,5026.8
XS Rating Curve= 0 ,0
Exp/Cntr=0.3,0.1

Type RM Length L Ch R = 1 ,1699    ,288,288,288
BEGIN DESCRIPTION:
Mapping XS 6e194e22
END DESCRIPTION:
XS GIS Cut Line= 2
      1964865.18     13913957.45      1965358.76     13913699.76
#Sta/Elev= 30
  4706.5 1694.84  4717.3 1691.99  4722.9 1694.34  4739.4  1688.5    4745 1690.52
  4761.4 1684.96  4767.1 1686.39  4783.5 1679.27  4789.2 1680.34  4805.6 1673.83
  4811.2 1674.59  4827.7 1668.51  4833.3 1669.23  4849.8 1662.94  4871.9 1661.39
  4877.5  1663.1  4960.2    1661  4982.3 1663.71  5026.5 1664.83  5033.4 1664.04
  5037.8    1661  5038.1  1660.5  5041.8    1661  5042.9 1663.54  5048.5 1664.13
  5087.1  1664.5  5153.3 1670.65  5175.5 1676.25    5236 1697.61  5263.3 1701.37
#Mann= 4 ,-1 , 0
  4706.5    .035       0  5037.8    .035       0  5041.8    .035       0
  5175.5     .07       0
Bank Sta=5037.8,5041.8
XS Rating Curve= 0 ,0
Exp/Cntr=0.3,0.1

Type RM Length L Ch R = 1 ,1411    ,191,191,191
BEGIN DESCRIPTION:
Stream0050 3.0
END DESCRIPTION:
XS GIS Cut Line= 3
      1964974.97     13914125.01        1965225.       13914075.
      1965524.97     13913875.02
#Sta/Elev= 30
  4740.3 1699.07  4760.7 1697.48  4791.3 1685.48  4801.5 1682.59  4903.5 1671.93
  4913.7 1669.68  4923.9 1665.82  4940.9 1662.24  4964.7 1658.46  4974.9 1653.38
  4985.1 1650.18  4998.3 1649.09  5000.8 1647.86    5001 1647.36  5004.8 1647.86
  5022.6 1648.64  5044.9 1647.98  5059.9 1649.01  5074.9 1647.99    5111 1648.68
  5172.2 1655.65  5247.7  1667.2  5255.2 1670.58  5261.2  1671.5  5276.2 1677.51
  5282.9 1681.28  5291.2 1685.89  5327.3 1697.49  5342.3    1701  5355.8 1701.61
#Mann= 8 ,-1 , 0
  4740.3     .07       0  4940.9    .035       0  5000.8    .035       0
  5004.8    .035       0  5022.6     .07       0  5044.9    .035       0
  5172.2     .07       0  5282.9      .1       0
Bank Sta=5000.8,5004.8
XS Rating Curve= 0 ,0
Exp/Cntr=0.3,0.1

Type RM Length L Ch R = 1 ,1220    ,279,279,279
BEGIN DESCRIPTION:
Mapping XS 39c210d3
END DESCRIPTION:
XS GIS Cut Line= 3
      1964916.12     13914169.23      1965401.12     13914275.58
       1965681.3     13914135.43
#Sta/Elev= 30
  4632.8 1701.37  4636.6 1697.74  4680.4 1695.01  4685.5 1690.79  4713.6 1686.56
  4723.8 1683.79  4734.5 1676.34  4744.3 1672.23  4785.2 1661.83  4815.9 1658.74
  4827.2 1655.49  4846.6 1653.94  4865.9 1655.07    4871  1652.2  4890.1 1652.92
  4958.7 1650.55  4990.3 1644.86    5154 1643.59  5154.3 1643.09    5158 1643.59
  5168.5 1644.39  5185.2 1650.27  5190.8 1649.73    5230 1658.66  5267.8 1660.98
  5309.9 1667.42  5366.1 1674.74  5386.5 1678.76  5421.9 1681.69  5442.6 1684.08
#Mann= 8 ,-1 , 0
  4632.8      .1       0  4890.1    .035       0  4990.3      .1       0
    5154     .05       0    5158      .1       0  5309.9     .07       0
  5366.1      .1       0  5421.9     .07       0
Bank Sta=5154,5158
XS Rating Curve= 0 ,0
Exp/Cntr=0.3,0.1

Type RM Length L Ch R = 1 ,941     ,465,465,465
BEGIN DESCRIPTION:
Stream0050 2.0
END DESCRIPTION:
XS GIS Cut Line= 4
        1965025.       13914275.        1965325.       13914475.
      1965490.34     13914481.33      1965960.39     13914362.31
#Sta/Elev= 30
  4639.3 1651.93  4649.5 1648.48  4652.8 1646.77  4667.8 1645.23    4797 1640.03
  4863.1  1641.7  4963.4 1639.44  5002.4 1638.57  5017.9 1634.34  5018.1 1633.84
  5021.9 1634.34  5031.3 1637.62  5165.1 1647.35  5190.8 1647.44    5214 1650.44
  5438.3 1666.02  5489.9  1672.9  5495.9 1675.68    5501 1674.73  5520.9 1679.14
  5551.8 1681.43  5572.4 1686.74  5577.9 1690.24    5583 1688.55  5593.1 1692.87
  5613.7 1696.44  5618.9 1700.55    5624  1698.2  5640.9 1702.85  5650.2 1705.46
#Mann= 7 ,-1 , 0
  4639.3     .07       0  4649.5      .1       0  4963.4      .1       0
  5017.9     .05       0  5021.9      .1       0  5031.3      .1       0
  5640.9     .07       0
#Block Obstruct= 2 , 0
         4863.68 1641.76
Bank Sta=5017.9,5021.9
XS Rating Curve= 0 ,0
Exp/Cntr=0.3,0.1

Type RM Length L Ch R = 1 ,476     ,383,383,383
BEGIN DESCRIPTION:
Stream0050 1.0
END DESCRIPTION:
XS GIS Cut Line= 5
      1964431.52     13914272.96      1964767.23      13914777.4
      1965074.37     13914904.57        1965225.       13914875.
      1965524.98     13914575.02
#Sta/Elev= 30
  3908.8 1741.99    3913 1741.99  3935.3 1731.34  3947.7 1721.62  3971.3 1708.89
  3998.8  1697.9  4013.9 1692.36  4043.4 1688.98    4065 1680.52  4079.4  1678.3
    4101 1667.81  4122.1 1660.65  4200.2 1641.49  4215.2 1638.93  4266.3 1632.32
  4324.6 1628.64  4374.5 1626.86  4460.5 1626.66  4494.4 1625.75  4607.4 1625.43
  4851.6 1626.76    4975    1628  4978.3 1624.98  4978.5 1624.48  4982.3 1624.98
  4990.5 1628.02  5174.1 1631.62  5255.2 1637.49  5325.9  1638.9  5424.9 1644.02
#Mann= 9 ,-1 , 0
  3908.8      .1       0  4324.6     .07       0  4460.5      .1       0
  4494.4     .07       0  4607.4    .035       0  4851.6      .1       0
  4978.3     .05       0  4982.3      .1       0  5174.1      .1       0
#Block Obstruct= 2 , 0
         4960.73 1627.99
Bank Sta=4978.3,4982.3
XS Rating Curve= 0 ,0
Exp/Cntr=0.3,0.1

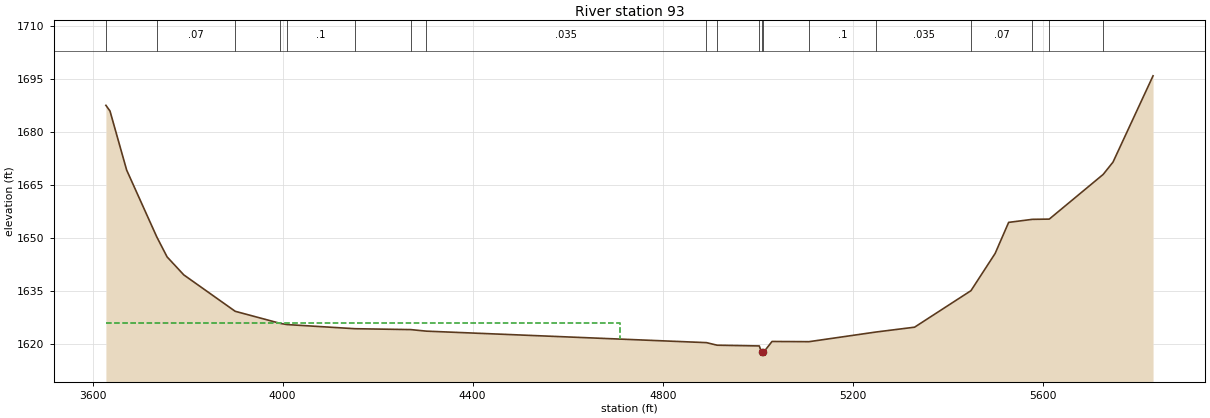
Type RM Length L Ch R = 1 ,93      ,0,0,0
BEGIN DESCRIPTION:
Stream0050 0.0
END DESCRIPTION:
XS GIS Cut Line= 4
       1964276.2     13914571.91      1964897.64     13915143.56
      1965702.22     13915126.59      1966113.16     13914754.05
#Sta/Elev= 30
  3628.1 1687.62  3636.7 1686.01  3671.8 1669.25  3735.2 1650.29  3756.9 1644.63
    3792 1639.53  3900.2  1629.2  3995.4 1625.76    4009 1625.44    4152 1624.26
  4269.3 1624.01  4302.4 1623.57    4892 1620.31  4914.5 1619.58  5003.2 1619.37
    5008 1617.55  5008.2 1617.05    5012 1617.55    5030 1620.64  5107.8 1620.58
  5248.8 1623.32    5330 1624.69  5448.7 1635.05  5499.6 1645.62    5528 1654.42
  5577.8 1655.28  5613.5 1655.35  5726.9 1668.02  5747.6 1671.51  5831.9 1695.99
#Mann= 19 ,-1 , 0
  3628.1      .1       0  3735.2     .07       0  3900.2      .1       0
  3995.4     .07       0    4009      .1       0    4152    .035       0
  4269.3      .1       0  4302.4    .035       0    4892     .07       0
  4914.5    .035       0  5003.2      .1       0    5008     .05       0
    5012      .1       0  5107.8      .1       0  5248.8    .035       0
  5448.7     .07       0  5577.8      .1       0  5613.5     .07       0
  5726.9      .1       0
#XS Ineff= 2 , 0
         4711.07 1625.82
Permanent Ineff=
       F       F
#Block Obstruct= 2 , 0
         4347.98 1623.93
Bank Sta=5008,5012
XS Rating Curve= 0 ,0
Exp/Cntr=0.3,0.1

Chan Stop Cuts=-1
Use User Specified Reach Order=0
Composite Channel Slope=5