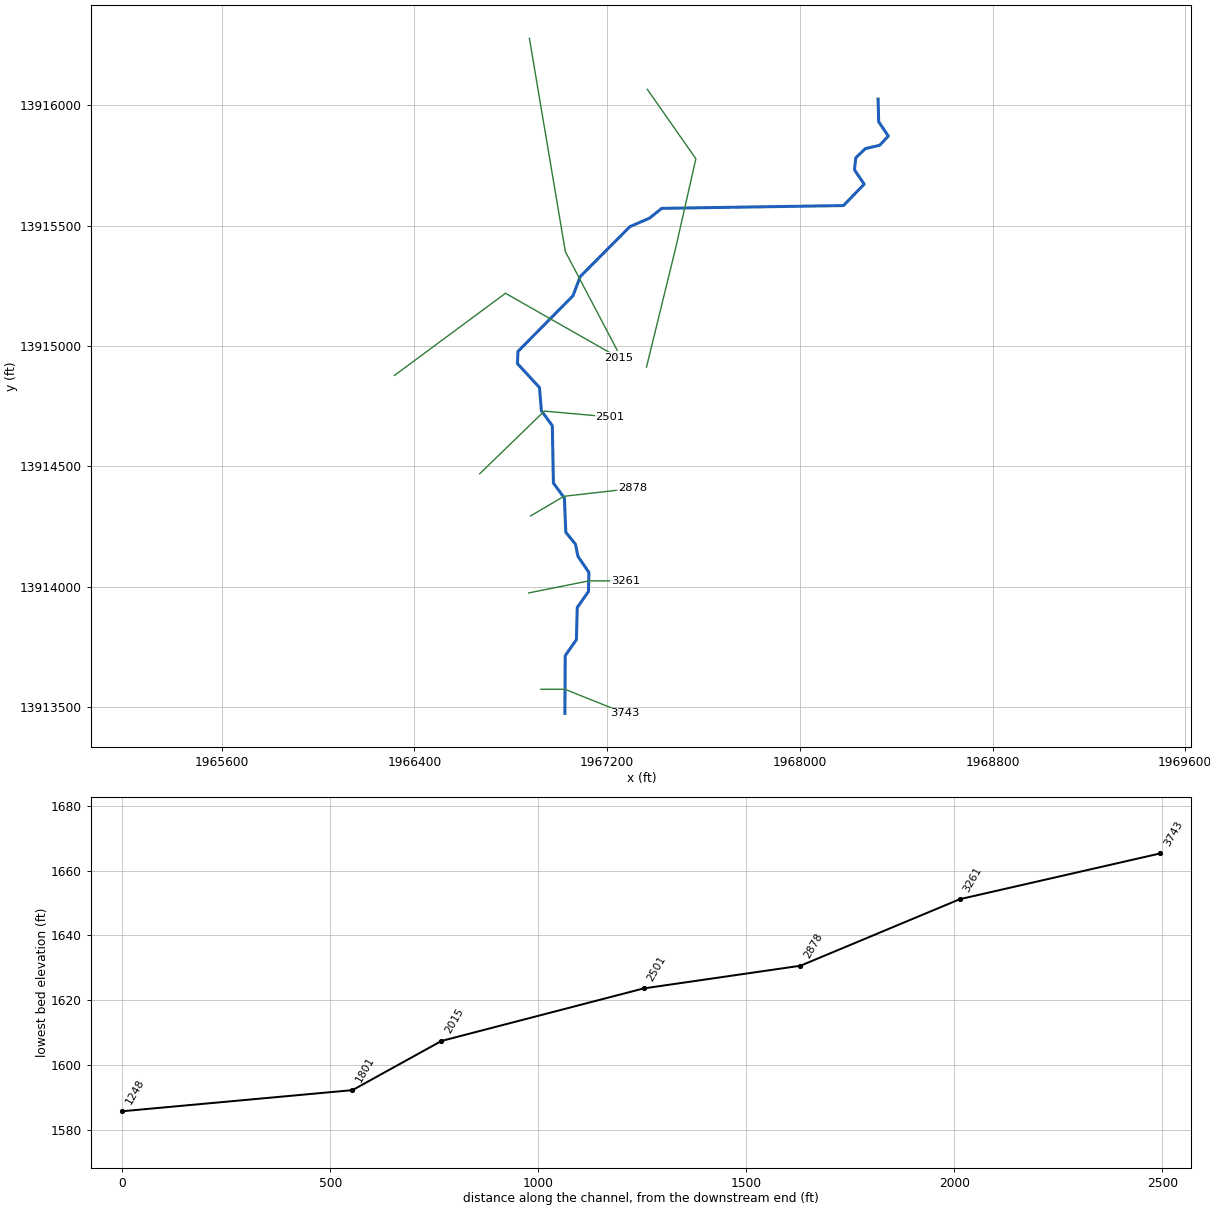
--- Stream0052.prj (project) ---

Proj Title=Stream0052 Base Level Engineering
Current Plan=p01
Default Exp/Contr=0.3,0.1
English Units
Geom File=g01
Flow File=f01
Plan File=p01
Y Axis Title=Elevation
X Axis Title(PF)=Main Channel Distance
X Axis Title(XS)=Station
BEGIN DESCRIPTION:
Stream0052
END DESCRIPTION:
DSS Export Rating Curves= 0
DSS Export Rating Curve Sorted= 0
DSS Export Volume Flow Curves= 0
DXF OffsetX= 0
DXF OffsetY= 0
DXF ScaleX= 1
DXF ScaleY= 10

--- Stream0052.p01 (plan) ---

Plan Title=Multiple Run
Short Identifier=Multiple
Geom File=g01
Flow File=f01
Subcritical Flow
K Sum by GR= 0
Std Step Tol= 0.01
Critical Tol= 0.01
Num of Std Step Trials= 20
Max Error Tol= 0.3
Flow Tol Ratio= 0.001
Split Flow NTrial= 30
Split Flow Tol= 0.02
Split Flow Ratio= 0.02
Log Output Level= 0
Friction Slope Method= 1
Unsteady Friction Slope Method= 2
Unsteady Bridges Friction Slope Method= 1
Parabolic Critical Depth
Global Vel Dist=  1 , 1 , 1
Global Log Level= 0
CheckData=True
Encroach Param= -1, 0, 0, 0
BEGIN DESCRIPTION:
Multiple Run
END DESCRIPTION:

--- Stream0052.f01 (steady flow) ---

Flow Title=Multiple
Number of Profiles=7
Profile Names=10-year,25-year,50-year,1pct_min,100-year,1pct_plu,500-year
River Rch & RM= Stream0052,Reach-1,3743
     478     769    1033     674    1345    2683    2242
Boundary for River Rch & Prof#=Stream0052,Reach-1,1
Up Type=0
Dn Type=3
Dn Slope=0.005
Boundary for River Rch & Prof#=Stream0052,Reach-1,2
Up Type=0
Dn Type=3
Dn Slope=0.005
Boundary for River Rch & Prof#=Stream0052,Reach-1,3
Up Type=0
Dn Type=3
Dn Slope=0.005
Boundary for River Rch & Prof#=Stream0052,Reach-1,4
Up Type=0
Dn Type=3
Dn Slope=0.005
Boundary for River Rch & Prof#=Stream0052,Reach-1,5
Up Type=0
Dn Type=3
Dn Slope=0.005
Boundary for River Rch & Prof#=Stream0052,Reach-1,6
Up Type=0
Dn Type=3
Dn Slope=0.005
Boundary for River Rch & Prof#=Stream0052,Reach-1,7
Up Type=0
Dn Type=3
Dn Slope=0.005

--- Stream0052.g01 (geometry) ---

Geom Title=Existing Conditions
Program Version=4.10

River Reach=Stream0052      ,Reach-1
Reach XY= 30
        1967025.       13913475.      1967026.22      13913714.5
      1967072.73     13913780.94      1967076.23     13913914.49
      1967122.83     13913980.98      1967124.63     13914059.73
      1967079.19     13914126.73      1967068.88     13914177.18
      1967028.76     13914226.56      1967022.73     13914369.06
      1966977.26     13914430.94      1966972.74     13914669.06
      1966927.36     13914730.98      1966919.46     13914827.42
      1966828.11     13914926.65      1966830.06     13914977.29
      1967058.35     13915208.33      1967088.63     13915288.21
      1967294.84     13915495.39      1967377.17     13915531.14
      1967426.55     13915571.25      1968181.23     13915582.81
      1968267.19     13915671.58      1968226.97     13915731.09
      1968232.39     13915781.33      1968272.44     13915819.25
      1968331.67     13915833.16      1968367.35     13915871.33
      1968327.35     13915930.76        1968325.       13916025.

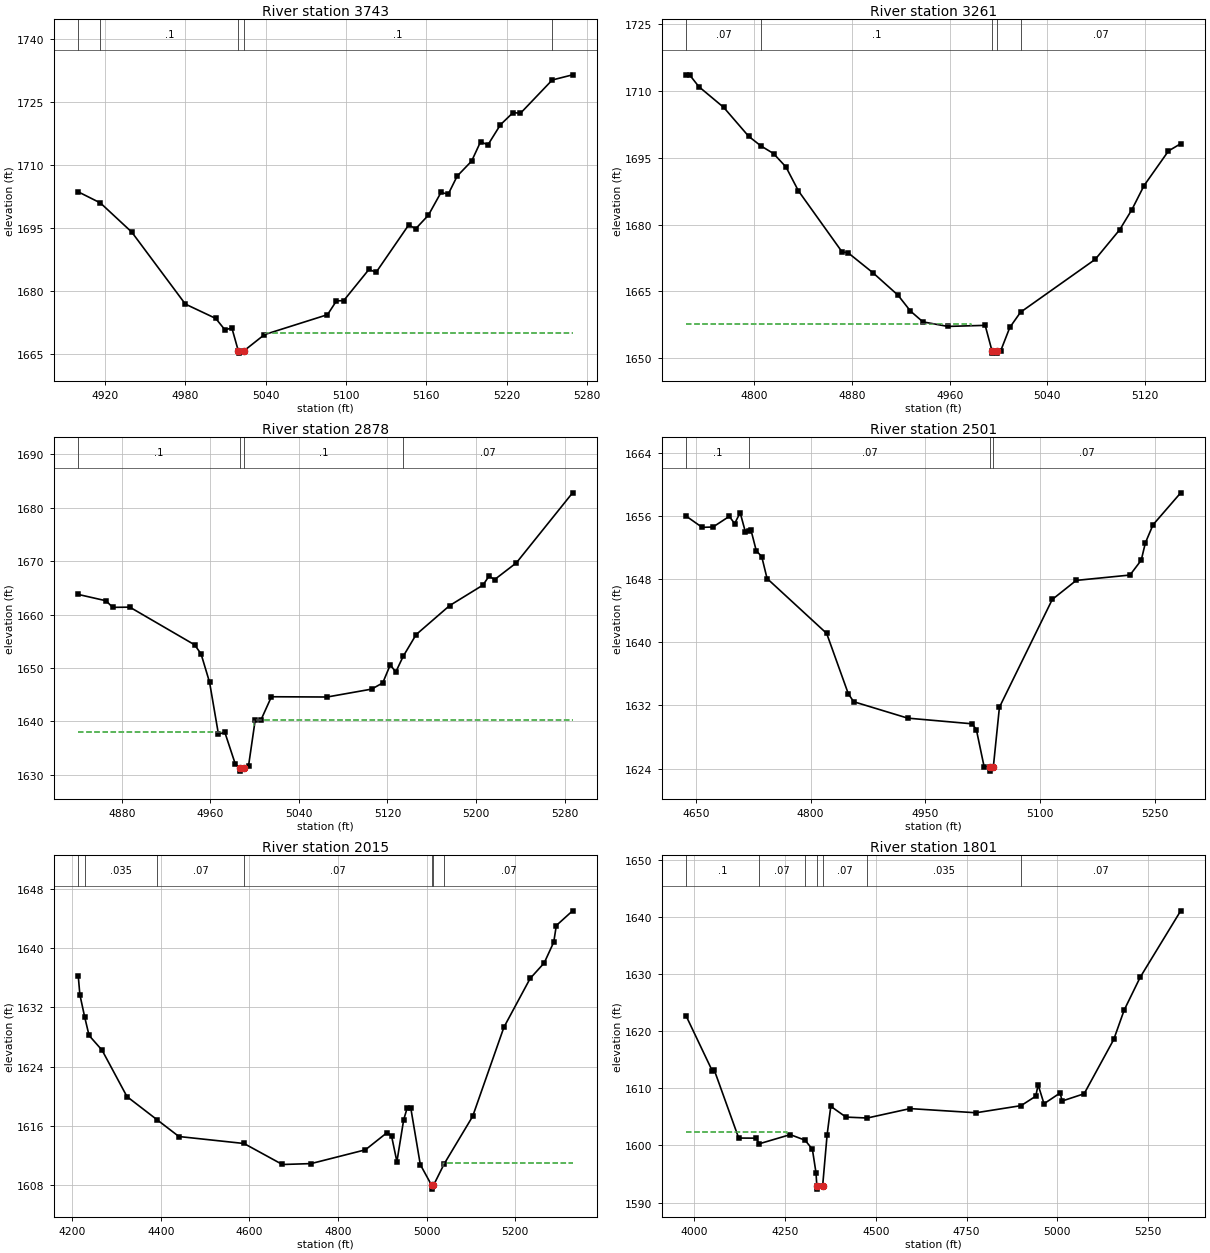
Type RM Length L Ch R = 1 ,3743    ,482,482,482
BEGIN DESCRIPTION:
Stream0052 4.0
END DESCRIPTION:
XS GIS Cut Line= 3
      1966924.96       13913575.        1967025.       13913575.
        1967275.       13913475.
#Sta/Elev= 30
    4900 1703.61  4916.5 1700.98    4940 1694.03    4980 1676.93  5002.7 1673.52
  5009.5 1670.84  5014.8 1671.21  5019.6 1665.77  5019.8 1665.27  5023.6 1665.77
  5039.1 1669.67  5086.2 1674.41  5092.9 1677.69  5098.3 1677.75  5117.2 1685.18
  5122.5 1684.47  5146.8 1695.71  5152.2 1694.87  5161.6 1698.07    5171 1703.47
  5176.4 1703.06  5183.1 1707.36  5193.9 1710.93  5200.6 1715.55    5206 1714.75
  5215.4 1719.56  5224.9 1722.47  5230.3 1722.27  5254.1  1730.2  5269.3 1731.43
#Mann= 5 ,-1 , 0
    4900     .07       0  4916.5      .1       0  5019.6     .05       0
  5023.6      .1       0  5254.1     .07       0
#XS Ineff= 2 , 0
                         5039.39         1670.11
Permanent Ineff=
       F       F
Bank Sta=5019.6,5023.6
XS Rating Curve= 0 ,0
Exp/Cntr=0.3,0.1

Type RM Length L Ch R = 1 ,3261    ,383,383,383
BEGIN DESCRIPTION:
Stream0052 3.0
END DESCRIPTION:
XS GIS Cut Line= 3
      1966874.97     13913974.99        1967125.       13914025.
      1967275.02       13914025.
#Sta/Elev= 30
  4744.2 1713.59  4746.8 1713.59  4754.4 1710.94  4774.8 1706.28  4795.2 1699.81
  4805.2 1697.66  4815.6 1695.93  4825.8 1692.92    4836 1687.56  4871.7 1673.89
  4876.8 1673.65  4897.2 1669.16  4917.6 1664.16  4927.8  1660.6    4938 1658.18
  4958.4 1657.16    4989  1657.4  4994.6 1651.67  4994.9 1651.17  4998.4 1651.17
  4998.6 1651.67  5001.7 1651.67  5009.2 1656.94    5018 1660.35  5079.2 1672.21
  5099.2 1678.84  5109.2 1683.35  5119.2 1688.76  5139.2 1696.52  5149.2 1698.14
#Mann= 5 ,-1 , 0
  4744.2     .07       0  4805.2      .1       0  4994.6     .05       0
  4998.6      .1       0    5018     .07       0
#XS Ineff= 2 , 0
          4977.6 1657.67
Permanent Ineff=
       F       F
Bank Sta=4994.6,4998.6
XS Rating Curve= 0 ,0
Exp/Cntr=0.3,0.1

Type RM Length L Ch R = 1 ,2878    ,377,377,377
BEGIN DESCRIPTION:
Stream0052 2.0
END DESCRIPTION:
XS GIS Cut Line= 3
      1966882.66     13914294.69      1967020.89       13914376.
      1967305.47     13914408.52
#Sta/Elev= 30
  4840.5 1663.76  4865.7 1662.57  4871.5 1661.34  4887.1 1661.38  4945.7 1654.32
  4951.5 1652.62  4959.2  1647.3  4967.2  1637.6    4973 1637.93  4982.4 1632.02
  4986.6 1631.17  4986.9 1630.67  4990.6 1631.17  4994.4 1631.63  5000.4 1640.19
  5005.5 1640.19  5015.1  1644.6  5065.4 1644.55  5105.7 1646.03  5115.7 1647.19
  5122.5 1650.56  5127.5 1649.24  5134.2 1652.17  5145.9 1656.24  5176.1 1661.66
  5206.3 1665.51  5211.8  1667.2  5216.8 1666.54  5236.5 1669.68  5287.3 1682.79
#Mann= 4 ,-1 , 0
  4840.5      .1       0  4986.6     .05       0  4990.6      .1       0
  5134.2     .07       0
#XS Ineff= 2 , 0
         4972.62 1638.04 4999.68         1640.32
Permanent Ineff=
       F       F
Bank Sta=4986.6,4990.6
XS Rating Curve= 0 ,0
Exp/Cntr=0.3,0.1

Type RM Length L Ch R = 1 ,2501    ,486,486,486
BEGIN DESCRIPTION:
Stream0052 1.0
END DESCRIPTION:
XS GIS Cut Line= 3
      1966671.25     13914469.47      1966939.59     13914729.67
      1967211.02     13914705.37
#Sta/Elev= 30
  4637.6 1655.95  4658.2 1654.55  4672.4 1654.59  4693.7 1655.94  4700.7 1655.02
  4707.9 1656.41  4714.8 1653.95  4718.9 1654.11    4722 1654.23    4729 1651.58
  4736.1 1650.85  4743.1 1648.07    4821 1641.12  4849.3 1633.48  4856.3 1632.47
    4927 1630.39  5011.4 1629.67  5016.8  1628.9  5026.9 1624.23  5034.9 1624.18
  5035.1 1623.68  5038.9 1624.18  5046.9 1631.77    5116 1645.42  5147.3 1647.83
  5217.6 1648.51  5232.3 1650.39  5237.7 1652.58  5247.7 1654.87  5283.9 1658.92
#Mann= 4 ,-1 , 0
  4637.6      .1       0  4718.9     .07       0  5034.9     .05       0
  5038.9     .07       0
Bank Sta=5034.9,5038.9
XS Rating Curve= 0 ,0
Exp/Cntr=0.3,0.1

Type RM Length L Ch R = 1 ,2015    ,214,214,214
BEGIN DESCRIPTION:
Stream0052 0.0
END DESCRIPTION:
XS GIS Cut Line= 3
      1966317.41     13914877.63      1966778.32     13915218.76
      1967249.63     13914950.56
#Sta/Elev= 30
  4213.6 1636.22  4217.2 1633.72  4228.2 1630.67    4238 1628.21  4267.3 1626.23
  4323.6 1619.97  4391.3 1616.86  4440.8 1614.59  4587.7 1613.65  4674.3 1610.82
    4739 1610.94  4861.7  1612.8  4910.7 1615.12  4920.8 1614.64  4932.8  1611.2
  4948.1 1616.85  4955.8 1618.39    4964 1618.48  4985.6 1610.81  5011.3    1608
  5011.6  1607.5  5015.3    1608  5039.3 1610.88  5103.8 1617.31  5174.4 1629.33
  5233.5 1635.89  5265.2 1637.98  5286.8 1640.79  5292.6 1643.03  5329.3 1645.01
#Mann= 7 ,-1 , 0
  4213.6     .07       0  4228.2    .035       0  4391.3     .07       0
  4587.7     .07       0  5011.3     .05       0  5015.3     .07       0
  5039.3     .07       0
#XS Ineff= 2 , 0
         4961.04 1617.43 5036.36         1611.04
Permanent Ineff=
       F       F
Bank Sta=5011.3,5015.3
XS Rating Curve= 0 ,0
Exp/Cntr=0.3,0.1

Type RM Length L Ch R = 1 ,1801    ,553,553,553
BEGIN DESCRIPTION:
Stream0052 T
END DESCRIPTION:
XS GIS Cut Line= 3
      1966877.59     13916276.96      1967026.89     13915391.59
      1967242.17     13914981.87
#Sta/Elev= 30
  3978.9  1622.6  4050.2 1613.07  4055.2  1613.3  4122.9  1601.3  4171.1 1601.28
  4179.2 1600.29  4264.8  1601.9  4305.4 1600.93  4325.7 1599.35  4335.8 1595.18
    4338 1592.85  4338.5 1592.35  4353.9 1592.85  4366.3 1601.88  4376.4 1606.86
  4418.2 1604.97  4476.8 1604.81  4594.6 1606.46  4776.1 1605.73  4900.3 1606.98
  4940.7 1608.64  4947.1 1610.63  4963.3 1607.31  5007.6 1609.19  5013.3 1607.79
  5073.8 1609.06  5155.3 1618.57    5184 1623.72  5228.1 1629.47  5339.6 1641.11
#Mann= 7 ,-1 , 0
  3978.9      .1       0  4179.2     .07       0  4305.4     .07       0
    4338     .05       0  4353.9     .07       0  4476.8    .035       0
  4900.3     .07       0
#XS Ineff= 2 , 0
         4257.14 1602.33
Permanent Ineff=
       F       F
Bank Sta=4338,4353.9
XS Rating Curve= 0 ,0
Exp/Cntr=0.3,0.1

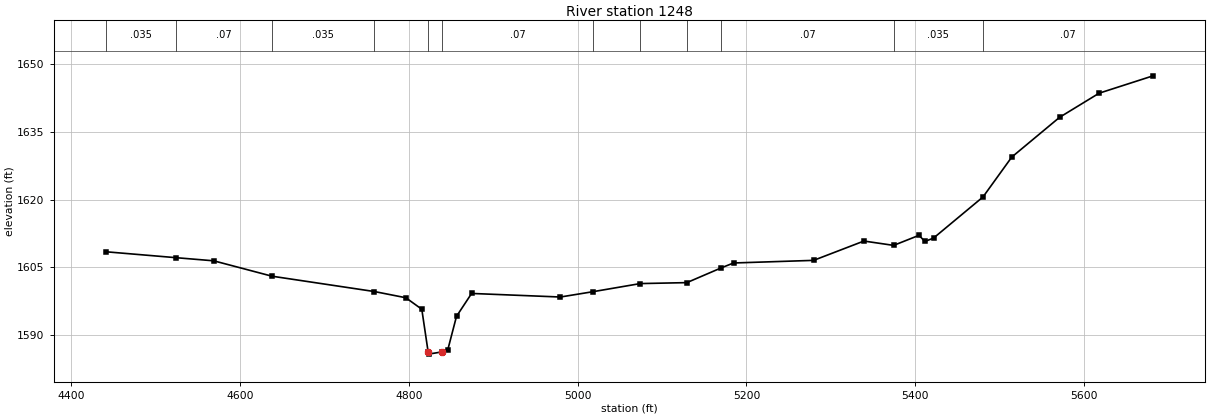
Type RM Length L Ch R = 1 ,1248    ,0,0,0
BEGIN DESCRIPTION:
Stream0552 T2
END DESCRIPTION:
XS GIS Cut Line= 4
      1967367.17     13916065.19      1967568.56       13915777.
      1967485.23     13915408.95      1967363.71     13914912.45
#Sta/Elev= 30
  4441.4 1608.47  4524.6 1607.16  4569.1 1606.47  4638.1 1603.07  4759.4 1599.68
  4796.6 1598.31  4815.5 1595.77    4823 1586.35  4823.5 1585.85  4839.6 1586.35
  4846.3 1586.82  4856.6  1594.2  4874.5 1599.26  4979.6 1598.47    5018 1599.64
  5074.2 1601.44  5129.4 1601.65  5170.2 1604.92  5184.7 1605.99  5279.5 1606.57
  5339.1 1610.84  5374.3 1609.88  5404.4 1612.11  5411.2 1610.74  5421.5 1611.49
  5480.1 1620.58  5514.2  1629.4  5570.8 1638.18  5617.6 1643.51  5681.5 1647.35
#Mann= 12 ,-1 , 0
  4441.4    .035       0  4524.6     .07       0  4638.1    .035       0
  4759.4     .07       0    4823     .05       0  4839.6     .07       0
    5018    .045       0  5074.2     .07       0  5129.4    .045       0
  5170.2     .07       0  5374.3    .035       0  5480.1     .07       0
Bank Sta=4823,4839.6
XS Rating Curve= 0 ,0
Exp/Cntr=0.3,0.1

Chan Stop Cuts=-1
Use User Specified Reach Order=0
Composite Channel Slope=5