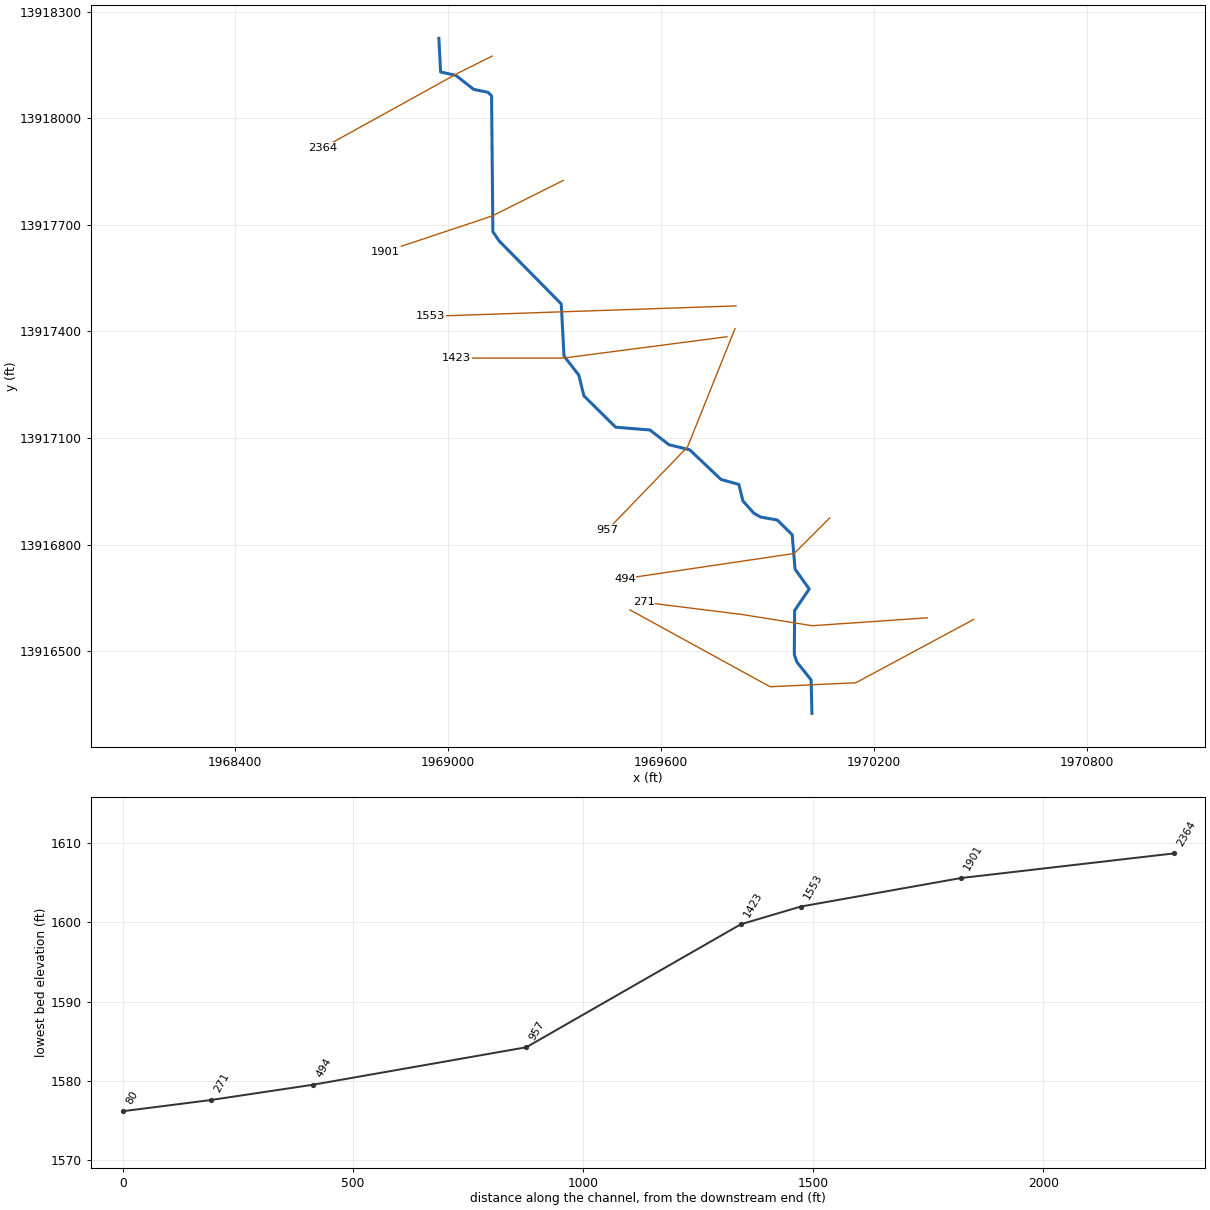
--- Stream0053.prj (project) ---

Proj Title=Stream0053 Base Level Engineering
Current Plan=p01
Default Exp/Contr=0.3,0.1
English Units
Geom File=g01
Flow File=f01
Plan File=p01
Y Axis Title=Elevation
X Axis Title(PF)=Main Channel Distance
X Axis Title(XS)=Station
BEGIN DESCRIPTION:
Stream0053
END DESCRIPTION:
DSS Export Rating Curves= 0
DSS Export Rating Curve Sorted= 0
DSS Export Volume Flow Curves= 0
DXF OffsetX= 0
DXF OffsetY= 0
DXF ScaleX= 1
DXF ScaleY= 10

--- Stream0053.p01 (plan) ---

Plan Title=Multiple Run
Short Identifier=Multiple
Geom File=g01
Flow File=f01
Subcritical Flow
K Sum by GR= 0
Std Step Tol= 0.01
Critical Tol= 0.01
Num of Std Step Trials= 20
Max Error Tol= 0.3
Flow Tol Ratio= 0.001
Split Flow NTrial= 30
Split Flow Tol= 0.02
Split Flow Ratio= 0.02
Log Output Level= 0
Friction Slope Method= 1
Unsteady Friction Slope Method= 2
Unsteady Bridges Friction Slope Method= 1
Parabolic Critical Depth
Global Vel Dist=  1 , 1 , 1
Global Log Level= 0
CheckData=True
Encroach Param= -1, 0, 0, 0
BEGIN DESCRIPTION:
Multiple Run
END DESCRIPTION:

--- Stream0053.f01 (steady flow) ---

Flow Title=Multiple
Program Version=4.10
Number of Profiles= 7
Profile Names=10-year,25-year,50-year,1pct_min,100-year,1pct_plu,500-year
River Rch & RM=Stream0053,Reach-1         ,2364
    1376    2383    3357    2289    4567    9113    8338
Boundary for River Rch & Prof#=Stream0053,Reach-1         , 1
Up Type= 0
Dn Type= 3
Dn Slope=0.008
Boundary for River Rch & Prof#=Stream0053,Reach-1         , 2
Up Type= 0
Dn Type= 3
Dn Slope=0.008
Boundary for River Rch & Prof#=Stream0053,Reach-1         , 3
Up Type= 0
Dn Type= 3
Dn Slope=0.008
Boundary for River Rch & Prof#=Stream0053,Reach-1         , 4
Up Type= 0
Dn Type= 3
Dn Slope=0.008
Boundary for River Rch & Prof#=Stream0053,Reach-1         , 5
Up Type= 0
Dn Type= 3
Dn Slope=0.008
Boundary for River Rch & Prof#=Stream0053,Reach-1         , 6
Up Type= 0
Dn Type= 3
Dn Slope=0.008
Boundary for River Rch & Prof#=Stream0053,Reach-1         , 7
Up Type= 0
Dn Type= 3
Dn Slope=0.008
DSS Import GetInterval= 0
DSS Import GetPeak= 0
DSS Import FillOption= 0

--- Stream0053.g01 (geometry) ---

Geom Title=Existing Conditions
Program Version=4.10

River Reach=Stream0053      ,Reach-1
Reach XY= 30
        1968975.       13918225.      1968979.99     13918130.28
       1969022.9     13918120.71      1969073.17     13918081.25
      1969113.33     13918073.06      1969123.38     13918063.19
      1969127.06     13917680.85       1969144.6     13917654.84
      1969319.53     13917477.45      1969327.25     13917330.93
      1969368.86     13917277.17      1969383.13     13917218.92
      1969472.56     13917130.52      1969569.03     13917122.67
      1969622.83     13917081.14      1969681.05     13917066.84
      1969769.26      13916983.3      1969819.37     13916969.35
      1969830.89      13916922.8      1969861.48     13916888.56
      1969880.92      13916877.5      1969927.55     13916869.25
      1969969.58     13916827.67      1969977.56      13916730.9
      1970017.44       13916675.      1969976.37     13916614.56
      1969975.49     13916490.22      1969983.09     13916468.93
       1970022.9     13916419.13        1970025.       13916325.

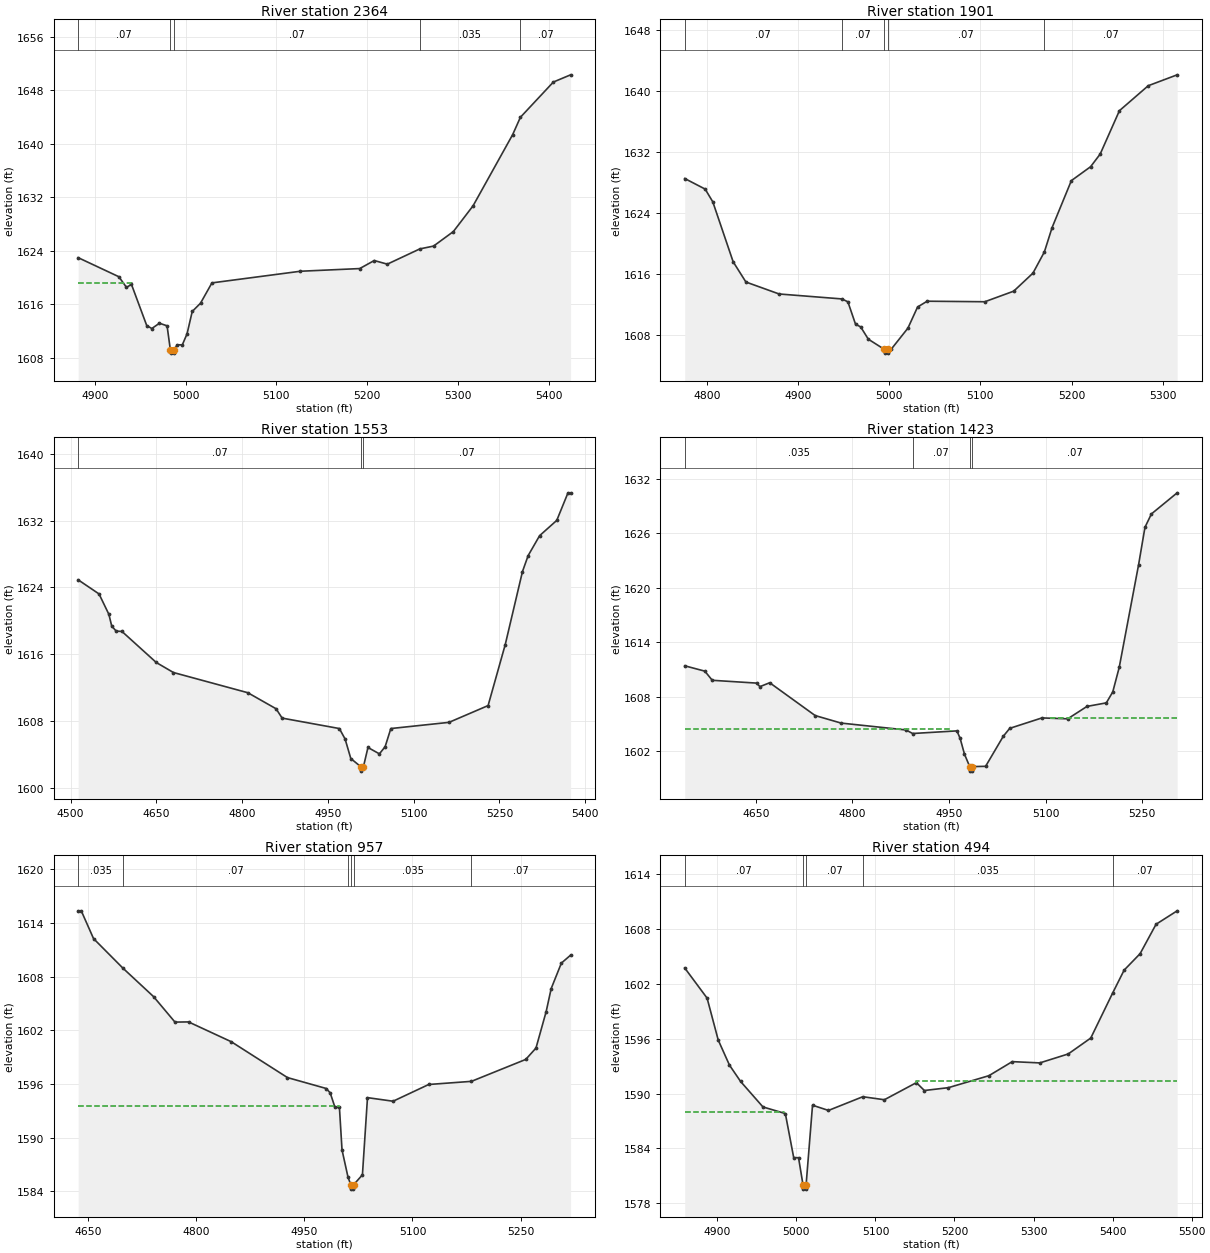
Type RM Length L Ch R = 1 ,2364    ,463,463,463
BEGIN DESCRIPTION:
Stream0053 5.0
END DESCRIPTION:
XS GIS Cut Line= 3
      1969125.04     13918175.02        1969025.       13918125.
      1968648.39     13917916.76
#Sta/Elev= 30
  4881.7 1622.98  4926.5 1620.13  4934.9 1618.54  4940.4 1618.98  4957.2 1612.83
  4962.8 1612.39  4971.2 1613.18  4979.6 1612.79  4983.2 1609.21  4983.4 1608.71
  4986.9 1608.71  4987.2 1609.21  4990.8 1609.95  4996.4 1609.95  5001.6  1611.6
  5007.3 1614.94  5016.4 1616.17    5029 1619.21  5126.4 1620.95  5191.7 1621.35
  5207.7 1622.55  5222.1 1622.01  5257.9 1624.29    5273 1624.71  5294.8 1626.88
  5316.5 1630.73  5360.1 1641.37  5368.6 1643.96  5404.9 1649.23  5423.9 1650.31
#Mann= 5 ,-1 , 0
  4881.7     .07       0  4983.2     .05       0  4987.2     .07       0
  5257.9    .035       0  5368.6     .07       0
#XS Ineff= 2 , 0
         4940.56 1619.16
Permanent Ineff=
       F       F
Bank Sta=4983.2,4987.2
XS Rating Curve= 0 ,0
Exp/Cntr=0.3,0.1

Type RM Length L Ch R = 1 ,1901    ,348,348,348
BEGIN DESCRIPTION:
Stream0053 4.0
END DESCRIPTION:
XS GIS Cut Line= 3
      1969325.03     13917825.01        1969125.       13917725.
      1968824.97     13917624.99
#Sta/Elev= 30
  4775.9 1628.54  4798.3 1627.15  4806.7 1625.47    4829  1617.6    4843 1614.94
  4879.4 1613.37  4948.2 1612.72  4954.8 1612.34  4963.2 1609.39  4968.8 1609.05
  4977.2 1607.43  4994.7  1606.1    4995  1605.6  4998.5  1605.6  4998.7  1606.1
  5002.2  1606.1  5020.6 1608.88  5031.2 1611.66  5041.7 1612.42  5104.9 1612.35
  5136.6 1613.74  5157.7 1616.11  5170.2 1618.89  5178.7  1622.1  5199.8 1628.26
  5220.9 1630.09  5231.4 1631.75  5252.5 1637.45  5284.1 1640.73  5315.8 1642.16
#Mann= 5 ,-1 , 0
  4775.9     .07       0  4948.2     .07       0  4994.7     .05       0
  4998.7     .07       0  5170.2     .07       0
Bank Sta=4994.7,4998.7
XS Rating Curve= 0 ,0
Exp/Cntr=0.3,0.1

Type RM Length L Ch R = 1 ,1553    ,130,130,130
BEGIN DESCRIPTION:
Stream0053 3.1
END DESCRIPTION:
XS GIS Cut Line= 2
      1969811.51      13917471.9      1968950.81     13917442.66
#Sta/Elev= 30
  4513.2 1624.91  4549.7 1623.22  4566.9 1620.78  4571.9 1619.37  4579.7 1618.77
  4589.8 1618.73  4649.8 1615.01  4679.8 1613.81  4809.9 1611.39  4859.3 1609.47
  4869.9 1608.35    4970  1607.1    4980 1605.85    4990 1603.51    5008  1602.5
  5008.2    1602    5012  1602.5    5020 1604.83    5040 1604.07    5050 1604.92
    5060  1607.1  5161.7 1607.84  5230.1 1609.85  5260.1 1617.16  5290.2  1625.9
  5300.2 1627.82  5320.2  1630.2  5350.2 1632.03  5369.8 1635.33  5374.4 1635.33
#Mann= 3 ,-1 , 0
  4513.2     .07       0    5008     .05       0    5012     .07       0
Bank Sta=5008,5012
XS Rating Curve= 0 ,0
Exp/Cntr=0.3,0.1

Type RM Length L Ch R = 1 ,1423    ,466,466,466
BEGIN DESCRIPTION:
Stream0053 3.0
END DESCRIPTION:
XS GIS Cut Line= 3
      1969785.89     13917385.08        1969325.       13917325.
      1969024.99       13917325.
#Sta/Elev= 30
  4539.5 1611.39  4570.7  1610.8  4582.3 1609.79  4651.2 1609.48  4656.3 1609.09
  4671.5 1609.52  4742.1  1605.9  4782.4 1605.07  4883.2 1604.31  4893.5 1603.92
  4962.3 1604.21  4967.3 1603.37    4974 1601.64  4982.1 1600.27  4982.4 1599.77
  4985.9 1599.77  4986.1 1600.27  5006.8  1600.3  5034.3 1603.62  5044.3 1604.49
  5094.3 1605.64  5134.3 1605.54  5164.3 1606.91  5194.3  1607.3  5204.3 1608.51
  5214.3 1611.21  5244.3  1622.5  5254.3 1626.67  5264.3 1628.14  5304.3 1630.47
#Mann= 4 ,-1 , 0
  4539.5    .035       0  4893.5     .07       0  4982.1     .05       0
  4986.1     .07       0
#XS Ineff= 2 , 0
         4953.45 1604.42 5106.29         1605.62
Permanent Ineff=
       F       F
Bank Sta=4982.1,4986.1
XS Rating Curve= 0 ,0
Exp/Cntr=0.3,0.1

Type RM Length L Ch R = 1 ,957     ,463,463,463
BEGIN DESCRIPTION:
Stream0053 2.0
END DESCRIPTION:
XS GIS Cut Line= 3
      1969808.63     13917407.94        1969675.       13917075.
      1969449.94     13916842.01
#Sta/Elev= 30
  4636.5 1615.35  4640.8 1615.35  4657.8 1612.25  4698.5 1608.95  4741.1 1605.76
  4770.7 1602.92  4789.5 1602.94  4848.7 1600.73  4926.7 1596.72  4980.5  1595.5
  4985.9 1595.01  4992.6 1593.38  4998.7 1593.38  5002.3 1588.64  5010.7 1585.56
  5014.5 1584.76  5014.7 1584.26  5018.2 1584.26  5018.5 1584.76  5030.6 1585.86
  5037.6 1594.48  5073.1 1594.08  5122.5 1595.95  5181.7  1596.3    5257 1598.75
  5271.2 1600.02  5285.3 1604.09  5292.3 1606.67  5306.4 1609.51  5319.2  1610.4
#Mann= 6 ,-1 , 0
  4636.5    .035       0  4698.5     .07       0  5010.7    .035       0
  5014.5     .05       0  5018.5    .035       0  5181.7     .07       0
#XS Ineff= 2 , 0
         4998.51 1593.56
Permanent Ineff=
       F       F
Bank Sta=5014.5,5018.5
XS Rating Curve= 0 ,0
Exp/Cntr=0.3,0.1

Type RM Length L Ch R = 1 ,494     ,223,223,223
BEGIN DESCRIPTION:
Stream0053 1.0
END DESCRIPTION:
XS GIS Cut Line= 3
      1970075.02     13916875.02        1969975.       13916775.
      1969498.64     13916704.48
#Sta/Elev= 30
  4858.7 1603.74    4887 1600.44  4901.1 1595.85  4915.3 1593.11  4929.4 1591.32
  4957.7 1588.53    4986 1587.81  4996.6 1582.98  5002.7 1582.98  5008.3 1580.04
  5008.5 1579.54    5012 1579.54  5012.3 1580.04  5020.4 1588.72  5040.6 1588.15
    5084 1589.65  5111.3 1589.32  5151.8 1591.19  5161.9 1590.33  5192.2 1590.64
  5243.5 1591.95  5273.1 1593.49  5307.9 1593.35  5343.9 1594.33  5372.4 1596.07
    5400 1600.98  5414.6  1603.5  5434.8  1605.3    5455 1608.52  5481.7 1609.99
#Mann= 5 ,-1 , 0
  4858.7     .07       0  5008.3     .05       0  5012.3     .07       0
    5084    .035       0    5400     .07       0
#XS Ineff= 2 , 0
         4984.62 1587.99 5151.05         1591.35
Permanent Ineff=
       F       F
Bank Sta=5008.3,5012.3
XS Rating Curve= 0 ,0
Exp/Cntr=0.3,0.1

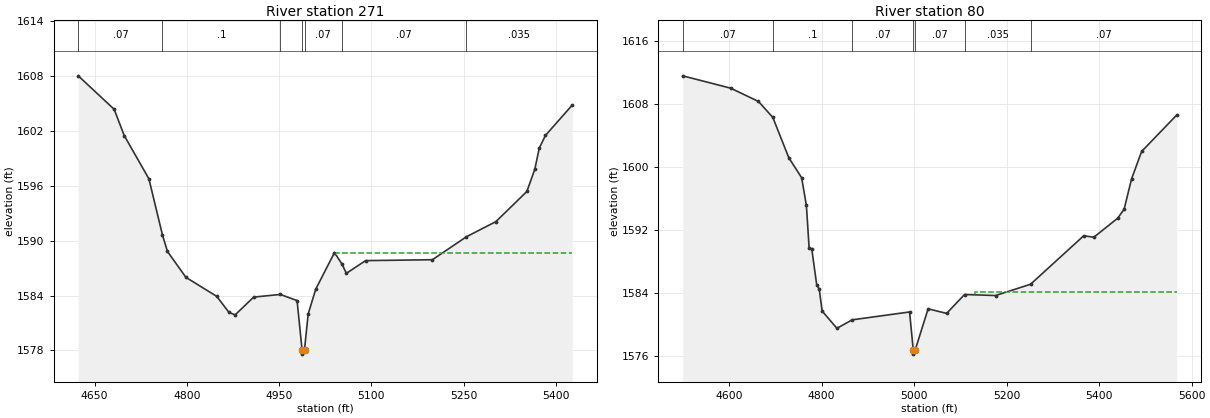
Type RM Length L Ch R = 1 ,271     ,191,191,191
BEGIN DESCRIPTION:
Mapping XS 9593c4af
END DESCRIPTION:
XS GIS Cut Line= 4
      1970349.65     13916593.88      1970025.77     13916571.75
      1969828.39     13916603.32      1969551.85     13916637.77
#Sta/Elev= 30
  4623.5 1608.05  4681.9 1604.39  4698.3 1601.51  4738.4 1596.78  4760.5 1590.62
  4768.5 1588.84  4798.6    1586  4848.7 1583.92  4868.7 1582.16  4878.7  1581.9
  4908.8 1583.84    4952 1584.13  4979.3 1583.46  4987.4  1578.1  4987.7  1577.6
  4991.4  1578.1  4997.4    1582  5009.7 1584.71  5040.1 1588.71  5052.3 1587.46
  5059.5 1586.44  5090.7 1587.83  5199.4 1587.93  5254.4 1590.43  5302.6  1592.1
    5353  1595.4    5366 1597.86  5373.1 1600.14  5383.2 1601.53  5426.7 1604.85
#Mann= 7 ,-1 , 0
  4623.5     .07       0  4760.5      .1       0    4952     .07       0
  4987.4     .05       0  4991.4     .07       0  5052.3     .07       0
  5254.4    .035       0
#XS Ineff= 2 , 0
                         5042.56         1588.69
Permanent Ineff=
       F       F
Bank Sta=4987.4,4991.4
XS Rating Curve= 0 ,0
Exp/Cntr=0.3,0.1

Type RM Length L Ch R = 1 ,80      ,0,0,0
BEGIN DESCRIPTION:
Stream0053 0.0
END DESCRIPTION:
XS GIS Cut Line= 4
      1970480.61     13916589.56      1970148.59     13916411.15
      1969907.38     13916399.97      1969513.05     13916616.17
#Sta/Elev= 30
  4499.5 1611.57  4603.3    1610  4663.4 1608.31  4694.4 1606.28  4729.1 1601.14
  4756.7 1598.62    4767 1595.09  4772.9  1589.7  4778.6 1589.58  4789.2 1585.04
  4794.8 1584.44    4801 1581.67    4833 1579.47    4866 1580.55  4990.1 1581.55
  4998.1 1576.69  4998.4 1576.19  5002.1 1576.69  5030.2 1581.95  5070.2 1581.37
    5109 1583.77  5176.1 1583.64  5251.6 1585.07  5366.7 1591.24  5388.5 1591.05
  5439.9 1593.46  5453.9 1594.59    5470 1598.45  5491.8 1601.95  5567.6 1606.58
#Mann= 7 ,-1 , 0
  4499.5     .07       0  4694.4      .1       0    4866     .07       0
  4998.1     .05       0  5002.1     .07       0    5109    .035       0
  5251.6     .07       0
#XS Ineff= 2 , 0
                         5131.91         1584.15
Permanent Ineff=
       F       F
Bank Sta=4998.1,5002.1
XS Rating Curve= 0 ,0
Exp/Cntr=0.3,0.1

Chan Stop Cuts=-1
Use User Specified Reach Order=0
Composite Channel Slope=5