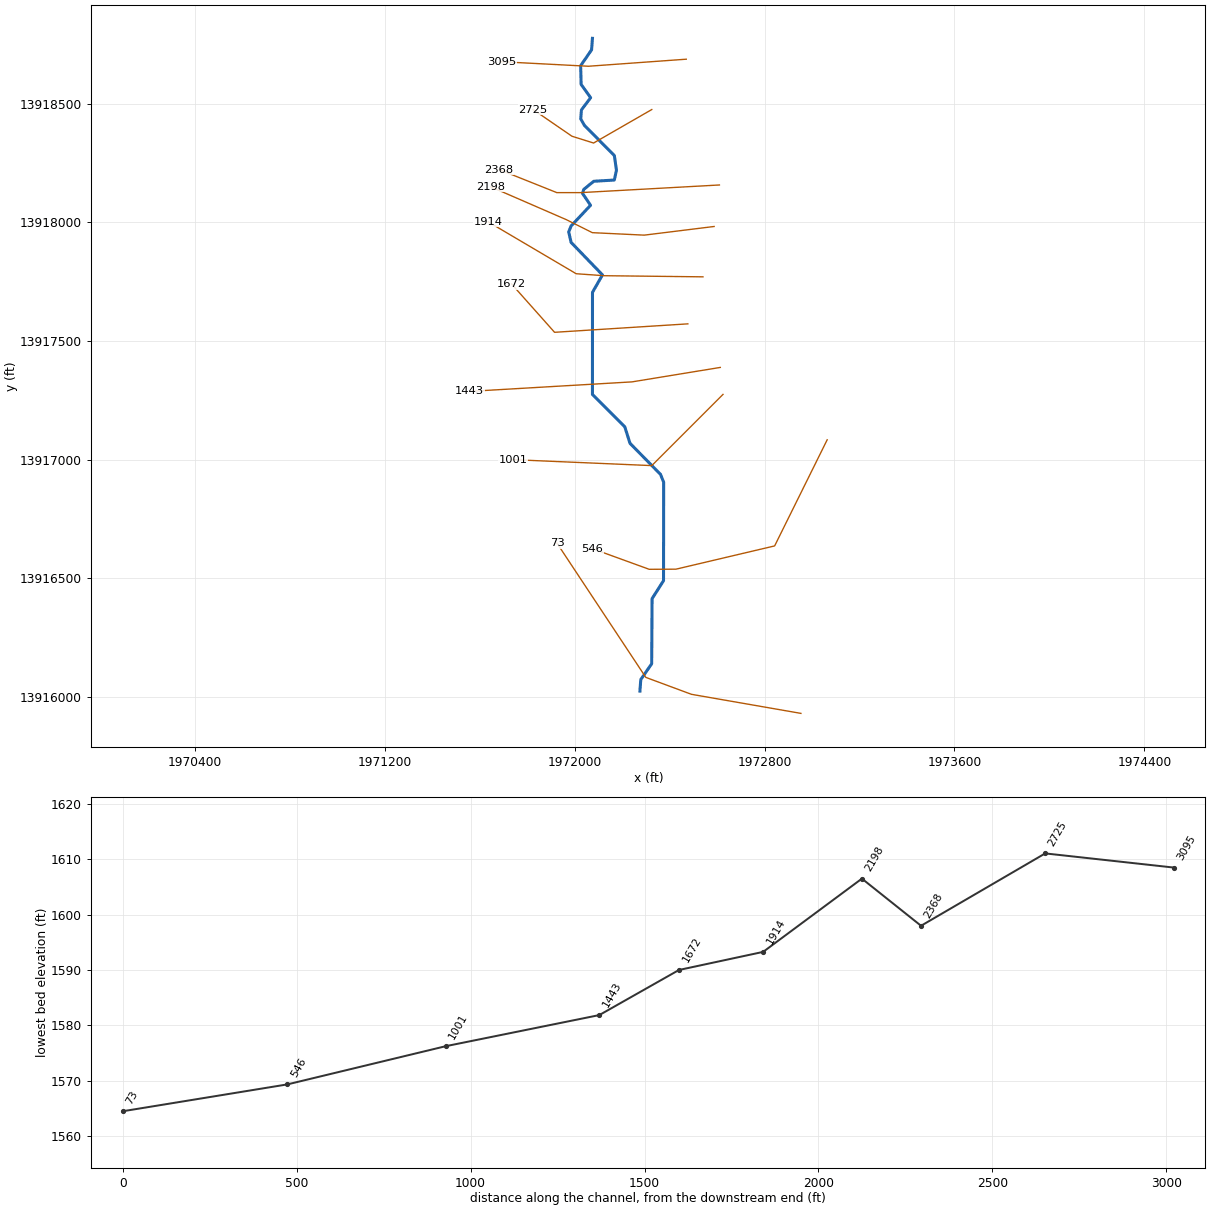
--- Stream0054.prj (project) ---

Proj Title=Stream0054 Base Level Engineering
Current Plan=p01
Default Exp/Contr=0.3,0.1
English Units
Geom File=g01
Flow File=f01
Plan File=p01
Y Axis Title=Elevation
X Axis Title(PF)=Main Channel Distance
X Axis Title(XS)=Station
BEGIN DESCRIPTION:
Stream0054
END DESCRIPTION:
DSS Export Rating Curves= 0
DSS Export Rating Curve Sorted= 0
DSS Export Volume Flow Curves= 0
DXF OffsetX= 0
DXF OffsetY= 0
DXF ScaleX= 1
DXF ScaleY= 10

--- Stream0054.p01 (plan) ---

Plan Title=Multiple Run
Short Identifier=Multiple
Geom File=g01
Flow File=f01
Subcritical Flow
K Sum by GR= 0
Std Step Tol= 0.01
Critical Tol= 0.01
Num of Std Step Trials= 20
Max Error Tol= 0.3
Flow Tol Ratio= 0.001
Split Flow NTrial= 30
Split Flow Tol= 0.02
Split Flow Ratio= 0.02
Log Output Level= 0
Friction Slope Method= 1
Unsteady Friction Slope Method= 2
Unsteady Bridges Friction Slope Method= 1
Parabolic Critical Depth
Global Vel Dist=  1 , 1 , 1
Global Log Level= 0
CheckData=True
Encroach Param= -1, 0, 0, 0
BEGIN DESCRIPTION:
Multiple Run
END DESCRIPTION:

--- Stream0054.f01 (steady flow) ---

Flow Title=Multiple
Program Version=4.10
Number of Profiles= 7
Profile Names=10-year,25-year,50-year,1pct_min,100-year,1pct_plu,500-year
River Rch & RM=Stream0054,Reach-1         ,3095
     248     388     510     328     654    1305    1061
River Rch & RM=Stream0054,Reach-1         ,1001
     392     632     849     556    1109    2213    1872
Boundary for River Rch & Prof#=Stream0054,Reach-1         , 1
Up Type= 0
Dn Type= 3
Dn Slope=0.005
Boundary for River Rch & Prof#=Stream0054,Reach-1         , 2
Up Type= 0
Dn Type= 3
Dn Slope=0.005
Boundary for River Rch & Prof#=Stream0054,Reach-1         , 3
Up Type= 0
Dn Type= 3
Dn Slope=0.005
Boundary for River Rch & Prof#=Stream0054,Reach-1         , 4
Up Type= 0
Dn Type= 3
Dn Slope=0.005
Boundary for River Rch & Prof#=Stream0054,Reach-1         , 5
Up Type= 0
Dn Type= 3
Dn Slope=0.005
Boundary for River Rch & Prof#=Stream0054,Reach-1         , 6
Up Type= 0
Dn Type= 3
Dn Slope=0.005
Boundary for River Rch & Prof#=Stream0054,Reach-1         , 7
Up Type= 0
Dn Type= 3
Dn Slope=0.005
DSS Import GetInterval= 0
DSS Import GetPeak= 0
DSS Import FillOption= 0

--- Stream0054.g01 (geometry) ---

Geom Title=Existing Conditions
Program Version=4.10

River Reach=Stream0054      ,Reach-1
Reach XY= 30
        1972075.       13918775.      1972071.35     13918726.51
      1972025.31     13918659.75      1972027.36     13918580.89
       1972067.4     13918524.99      1972028.57     13918473.35
      1972025.65     13918435.64      1972041.23     13918408.33
      1972167.26     13918281.12      1972176.07      13918219.5
      1972167.11     13918178.03       1972080.6     13918172.81
      1972038.48     13918138.75      1972033.08     13918121.87
      1972066.98     13918071.68      1971985.22     13917984.68
       1971974.9     13917959.64      1971985.17     13917915.32
      1972117.21     13917778.42      1972075.19     13917705.02
        1972075.       13917275.      1972211.37     13917138.21
      1972233.16     13917068.95      1972361.63     13916938.32
      1972375.04     13916905.02      1972374.48     13916490.22
      1972326.22      13916414.5      1972324.55     13916140.19
      1972278.65     13916073.49        1972275.       13916025.

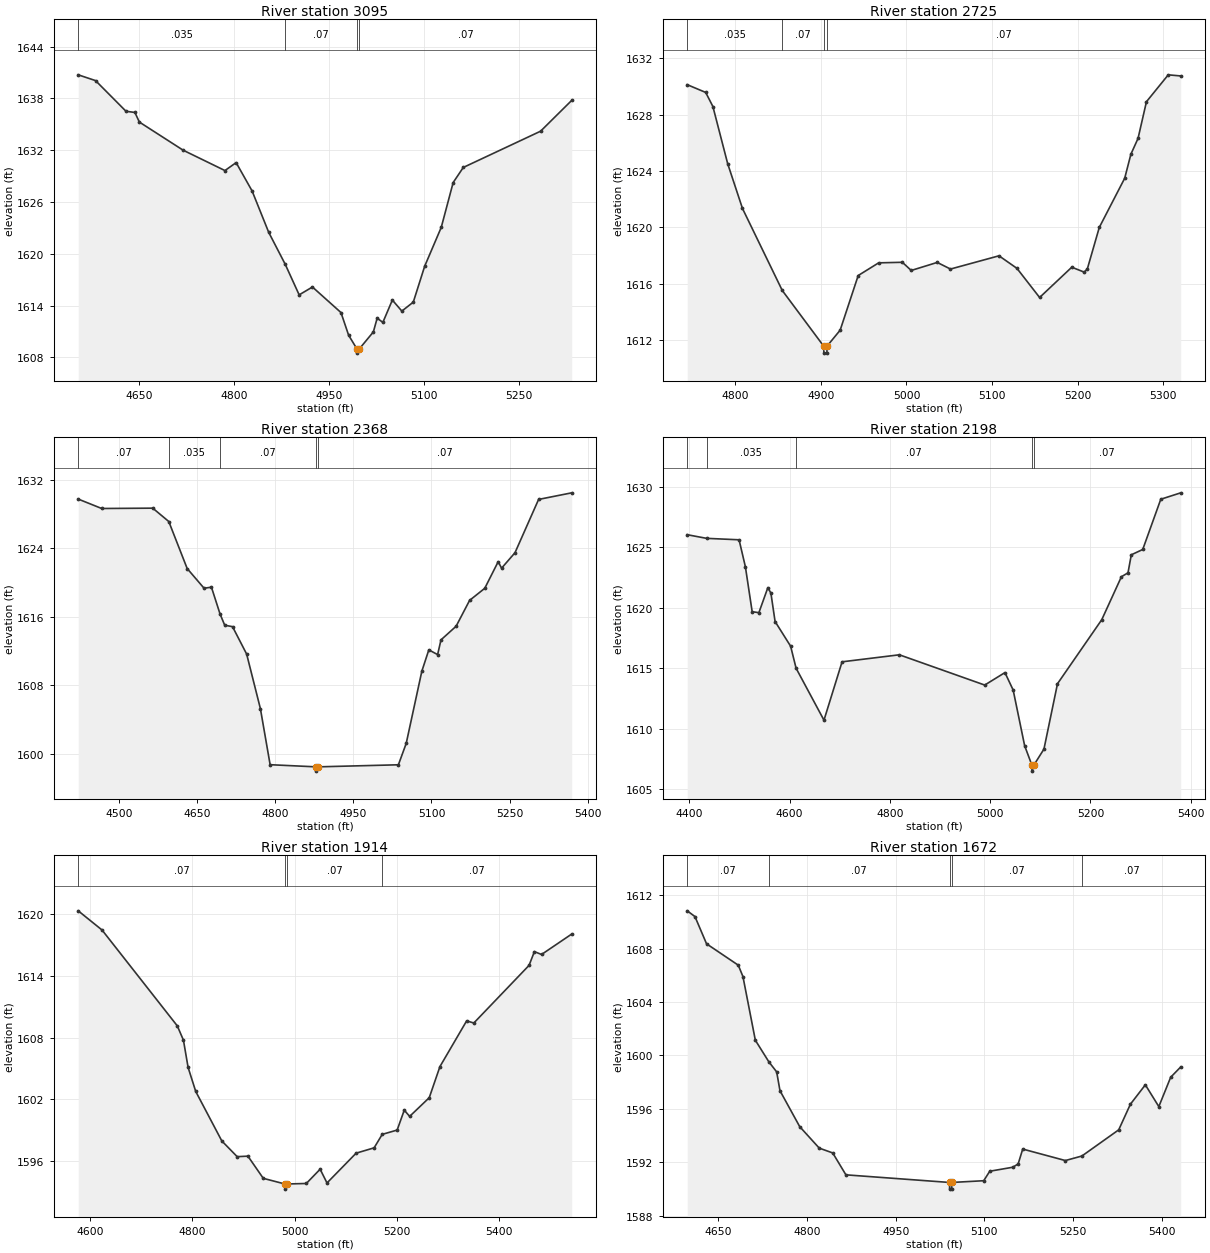
Type RM Length L Ch R = 1 ,3095    ,370,370,370
BEGIN DESCRIPTION:
Stream0054 6.0
END DESCRIPTION:
XS GIS Cut Line= 3
      1972470.34     13918687.12      1972057.86     13918657.42
       1971691.9     13918676.49
#Sta/Elev= 30
  4553.8 1640.74  4581.2 1640.07  4629.3 1636.52  4643.4 1636.38  4650.4 1635.27
  4719.6 1632.01  4785.7 1629.65  4803.4 1630.57  4828.6 1627.29  4854.9 1622.49
    4881 1618.79    4903 1615.25    4924 1616.16  4969.1  1613.2  4981.2 1610.57
  4994.2    1609  4994.5  1608.5  4998.2    1609  5020.3 1610.96  5026.3 1612.55
  5035.3 1612.06  5050.3 1614.65  5065.3 1613.37  5083.4 1614.41  5101.4 1618.57
  5127.6 1623.07  5146.4 1628.26  5162.4 1630.01  5284.6 1634.21  5333.8 1637.78
#Mann= 4 ,-1 , 0
  4553.8    .035       0    4881     .07       0  4994.2     .05       0
  4998.2     .07       0
Bank Sta=4994.2,4998.2
XS Rating Curve= 0 ,0
Exp/Cntr=0.3,0.1

Type RM Length L Ch R = 1 ,2725    ,357,357,357
BEGIN DESCRIPTION:
Stream0054 5.0
END DESCRIPTION:
XS GIS Cut Line= 4
      1972325.02     13918475.01      1972079.82     13918333.94
      1971988.68     13918362.58      1971824.99       13918475.
#Sta/Elev= 30
  4743.7 1630.12  4765.3 1629.57  4773.7 1628.57    4791 1624.51  4808.3 1621.33
  4854.8 1615.51  4903.2 1611.56  4903.5 1611.06    4907 1611.06  4907.2 1611.56
  4922.5 1612.69  4943.6 1616.57  4967.5 1617.47  4995.2 1617.51  5005.6 1616.93
    5036  1617.5  5051.5 1617.03  5108.2 1617.97  5129.2 1617.08  5155.7 1615.01
  5193.3 1617.16  5207.9 1616.81  5211.5 1617.04  5225.5 1619.99  5255.2 1623.48
  5262.4 1625.18  5270.8 1626.31  5280.6 1628.91  5306.1 1630.82  5320.7 1630.74
#Mann= 4 ,-1 , 0
  4743.7    .035       0  4854.8     .07       0  4903.2     .05       0
  4907.2     .07       0
Bank Sta=4903.2,4907.2
XS Rating Curve= 0 ,0
Exp/Cntr=0.3,0.1

Type RM Length L Ch R = 1 ,2368    ,170,170,170
BEGIN DESCRIPTION:
Stream0054 4.0
END DESCRIPTION:
XS GIS Cut Line= 4
      1972609.91     13918157.23        1972025.       13918125.
        1971925.       13918125.      1971681.91     13918222.19
#Sta/Elev= 30
  4421.7 1629.75  4466.8 1628.65  4564.8 1628.69  4595.6 1627.13  4630.9 1621.64
  4663.3 1619.34  4677.5 1619.46  4694.1 1616.32    4703 1615.02    4718 1614.85
  4745.1 1611.65  4771.5 1605.28  4790.2 1598.73  4878.3 1598.48  4878.5 1597.98
  4882.3 1598.48  5036.5 1598.72  5051.5 1601.22  5081.5 1609.65  5094.9 1612.14
  5111.8 1611.59  5118.3 1613.31  5147.3  1614.9  5173.2 1617.92  5202.3 1619.33
  5228.1 1622.44  5234.6 1621.68  5260.4 1623.49  5305.7 1629.71  5369.3 1630.48
#Mann= 5 ,-1 , 0
  4421.7     .07       0  4595.6    .035       0  4694.1     .07       0
  4878.3     .05       0  4882.3     .07       0
Bank Sta=4878.3,4882.3
XS Rating Curve= 0 ,0
Exp/Cntr=0.3,0.1

Type RM Length L Ch R = 1 ,2198    ,284,284,284
BEGIN DESCRIPTION:
Stream0054 3.1
END DESCRIPTION:
XS GIS Cut Line= 5
      1972587.64     13917982.38      1972293.36     13917945.92
      1972074.61     13917956.33      1971965.24     13918011.02
      1971647.53     13918149.04
#Sta/Elev= 30
  4395.9 1626.03  4434.5 1625.73  4499.3 1625.61  4511.9 1623.38  4525.4 1619.67
  4538.8 1619.59  4556.7 1621.66  4562.8  1621.2  4571.1 1618.86  4602.1 1616.82
    4613    1615  4668.6 1610.71  4704.7 1615.53  4818.9 1616.11  4989.2 1613.61
  5029.5 1614.64  5045.9  1613.2  5068.8  1608.6  5083.2    1607  5083.4  1606.5
  5087.2    1607  5107.3 1608.32  5134.3 1613.72  5222.6 1619.01  5261.8 1622.56
  5274.9 1622.88  5281.5 1624.37  5304.3 1624.81  5340.3 1628.96  5380.1 1629.49
#Mann= 5 ,-1 , 0
  4395.9     .07       0  4434.5    .035       0    4613     .07       0
  5083.2     .05       0  5087.2     .07       0
Bank Sta=5083.2,5087.2
XS Rating Curve= 0 ,0
Exp/Cntr=0.3,0.1

Type RM Length L Ch R = 1 ,1914    ,242,242,242
BEGIN DESCRIPTION:
Stream0054 3.0
END DESCRIPTION:
XS GIS Cut Line= 4
      1972540.58     13917770.25        1972125.       13917775.
      1972006.53     13917783.32      1971636.21     13918001.74
#Sta/Elev= 30
    4577 1620.35  4623.6 1618.48  4770.6 1609.15  4782.6 1607.76  4791.7 1605.11
  4806.6 1602.77  4857.6 1597.95  4887.6 1596.42  4908.6 1596.47  4938.6 1594.31
  4980.9 1593.76  4981.1 1593.26  4984.9 1593.76  5022.7 1593.81  5049.7  1595.2
  5063.1 1593.86    5120 1596.76  5155.2 1597.28    5171 1598.59  5200.2 1599.01
  5214.1 1600.95  5224.6 1600.34  5262.9 1602.16  5283.8 1605.19    5336 1609.64
    5350 1609.43  5457.9 1615.04  5468.4 1616.38  5482.3  1616.1  5541.3 1618.09
#Mann= 4 ,-1 , 0
    4577     .07       0  4980.9     .05       0  4984.9     .07       0
    5171     .07       0
Bank Sta=4980.9,4984.9
XS Rating Curve= 0 ,0
Exp/Cntr=0.3,0.1

Type RM Length L Ch R = 1 ,1672    ,229,229,229
BEGIN DESCRIPTION:
Stream0054 2.6
END DESCRIPTION:
XS GIS Cut Line= 3
      1972477.08     13917572.18      1971915.48     13917536.57
      1971734.22     13917740.27
#Sta/Elev= 30
  4597.1 1610.83  4610.2  1610.4  4629.8 1608.36  4683.5 1606.76  4691.4 1605.91
  4712.4 1601.14  4735.3 1599.52  4748.5 1598.77  4754.1 1597.36  4787.5 1594.67
  4820.6 1593.06  4843.4  1592.7  4865.7 1591.06  5041.1 1590.49  5041.3 1589.99
  5044.8 1589.99  5045.1 1590.49    5099 1590.62  5109.2 1591.33  5148.3 1591.63
  5157.3 1591.88    5165 1592.99  5237.2 1592.13  5265.2 1592.47  5327.5 1594.43
  5347.3 1596.35  5372.6  1597.8  5395.4 1596.17  5415.5 1598.37  5432.5 1599.14
#Mann= 5 ,-1 , 0
  4597.1     .07       0  4735.3     .07       0  5041.1     .05       0
  5045.1     .07       0  5265.2     .07       0
Bank Sta=5041.1,5045.1
XS Rating Curve= 0 ,0
Exp/Cntr=0.3,0.1

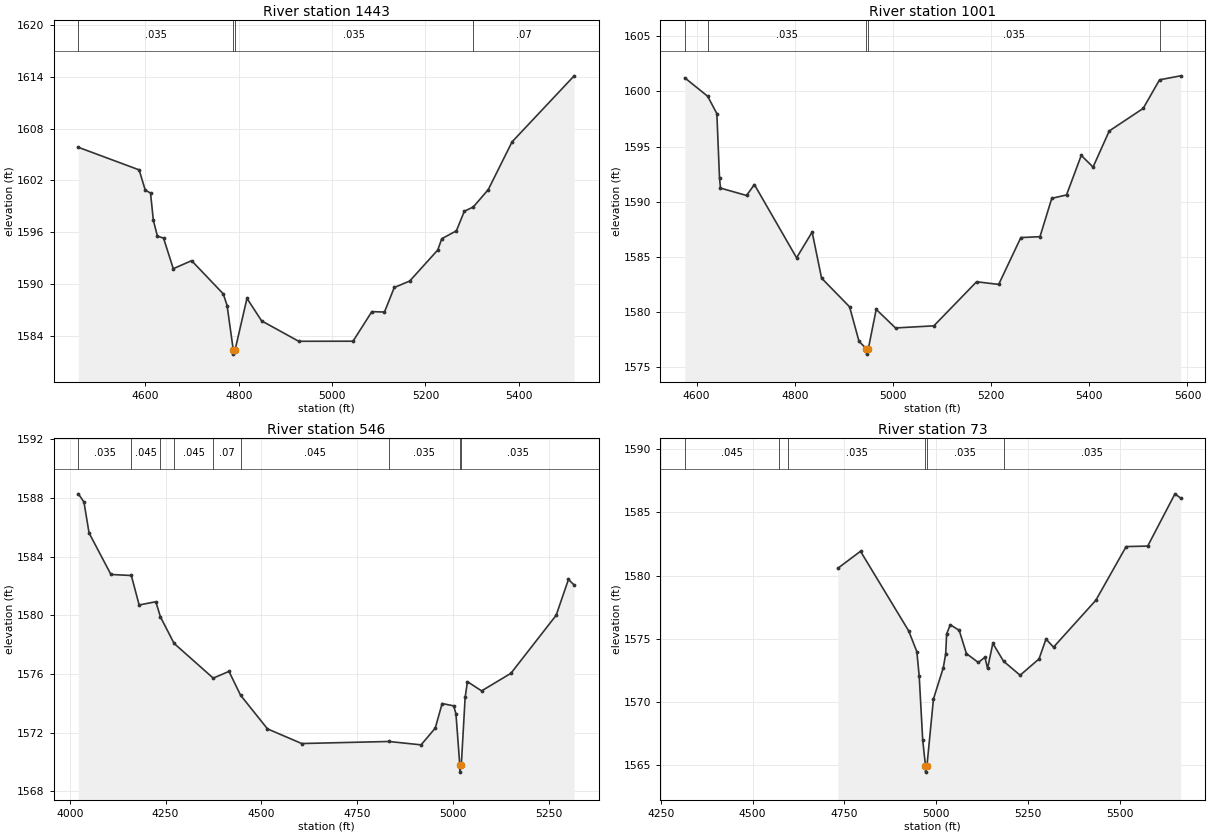
Type RM Length L Ch R = 1 ,1443    ,442,442,442
BEGIN DESCRIPTION:
Stream0054 2.5
END DESCRIPTION:
XS GIS Cut Line= 3
      1972613.66     13917388.62       1972241.9     13917327.74
      1971557.18     13917287.64
#Sta/Elev= 30
  4456.1 1605.83  4586.4 1603.21  4599.5 1600.86  4610.8 1600.53  4616.9 1597.36
  4625.6 1595.52  4638.7  1595.3  4659.6 1591.75  4698.9 1592.68  4766.7 1588.83
  4774.9 1587.48  4788.1 1582.34  4788.4 1581.84  4792.1 1582.34  4817.5 1588.31
  4848.9  1585.7  4928.4 1583.33  5044.8 1583.34  5085.1 1586.77  5112.2 1586.72
  5133.2 1589.57  5166.3 1590.32  5226.4 1593.92    5235 1595.23  5266.3 1596.14
  5283.3 1598.41  5302.5 1598.91  5334.6 1600.92  5385.6 1606.46  5518.7 1614.12
#Mann= 4 ,-1 , 0
  4456.1    .035       0  4788.1    .035       0  4792.1    .035       0
  5302.5     .07       0
Bank Sta=4788.1,4792.1
XS Rating Curve= 0 ,0
Exp/Cntr=0.3,0.1

Type RM Length L Ch R = 1 ,1001    ,455,455,455
BEGIN DESCRIPTION:
Stream0054 2.0
END DESCRIPTION:
XS GIS Cut Line= 3
      1972624.99     13917274.99        1972325.       13916975.
      1971739.78     13917000.09
#Sta/Elev= 30
    4576 1601.22  4622.6 1599.55  4641.3 1597.98  4646.7 1592.15  4648.7 1591.24
  4701.8 1590.57  4717.7 1591.56  4803.7 1584.93  4835.4 1587.26  4854.6 1583.09
  4911.7 1580.49  4930.9 1577.36  4945.9 1576.71  4946.2 1576.21  4949.9 1576.71
  4965.9 1580.26  5005.2 1578.58  5083.3 1578.77  5170.4 1582.76  5215.4 1582.52
  5260.5 1586.76  5299.5 1586.84  5323.5 1590.31  5353.6 1590.62  5383.6  1594.2
  5407.6 1593.14  5440.6 1596.41  5509.7 1598.45  5543.1 1601.04    5586  1601.4
#Mann= 5 ,-1 , 0
    4576     .07       0  4622.6    .035       0  4945.9    .035       0
  4949.9    .035       0  5543.1     .07       0
Bank Sta=4945.9,4949.9
XS Rating Curve= 0 ,0
Exp/Cntr=0.3,0.1

Type RM Length L Ch R = 1 ,546     ,473,473,473
BEGIN DESCRIPTION:
Stream0054 1.0
END DESCRIPTION:
XS GIS Cut Line= 5
       1973063.9     13917083.72      1972842.55     13916636.68
      1972426.83     13916538.68      1972314.13     13916538.15
      1972074.97     13916625.01
#Sta/Elev= 30
  4022.5 1588.29  4037.2 1587.73  4050.5 1585.62  4107.5 1582.79  4160.7 1582.72
  4181.1 1580.71  4224.6 1580.93  4236.6  1579.9  4272.2 1578.09  4374.3 1575.72
  4415.4 1576.18  4445.5 1574.56  4515.8 1572.26  4605.1 1571.26  4832.4  1571.4
  4916.4 1571.17  4953.3 1572.31  4971.3 1573.99  5001.3 1573.83  5007.3 1573.29
  5017.3 1569.81  5017.5 1569.31  5021.3 1569.81  5031.3 1574.41  5037.3 1575.48
  5074.2 1574.85  5150.7 1576.05  5268.7 1580.01  5300.7 1582.45  5315.6 1582.07
#Mann= 9 ,-1 , 0
  4022.5    .035       0  4160.7    .045       0  4236.6     .07       0
  4272.2    .045       0  4374.3     .07       0  4445.5    .045       0
  4832.4    .035       0  5017.3    .035       0  5021.3    .035       0
#Block Obstruct= 2 , 0
         4976.82 1573.69
Bank Sta=5017.3,5021.3
XS Rating Curve= 0 ,0
Exp/Cntr=0.3,0.1

Type RM Length L Ch R = 1 ,73      ,0,0,0
BEGIN DESCRIPTION:
Stream0054 0.0
END DESCRIPTION:
XS GIS Cut Line= 4
      1972953.27      13915931.2      1972492.08      13916011.5
      1972299.87     13916082.82      1971925.51     13916648.41
#Sta/Elev= 30
  4732.4 1580.58    4794 1581.92  4925.2 1575.63  4947.5 1573.99    4954 1572.05
  4963.6 1566.98  4971.1 1564.96  4971.4 1564.46  4975.1 1564.96  4992.8 1570.24
  5019.7 1572.72  5026.2 1573.82  5028.7 1575.38  5038.7 1576.11    5063 1575.67
  5082.7 1573.83  5115.1 1573.13  5133.1 1573.54  5140.3 1572.66  5154.7 1574.64
  5183.8 1573.23    5229 1572.12  5280.6 1573.41  5299.6 1574.98  5320.1 1574.34
  5435.5 1578.05    5518 1582.29  5576.8 1582.33  5651.1 1586.46  5666.5 1586.12
#Mann= 6 ,-1 , 0
  4315.1    .045       0  4572.2    .035       0  4597.7    .035       0
  4971.1    .035       0  4975.1    .035       0  5183.8    .035       0
Bank Sta=4971.1,4975.1
XS Rating Curve= 0 ,0
Exp/Cntr=0.3,0.1

Chan Stop Cuts=-1
Use User Specified Reach Order=0
Composite Channel Slope=5