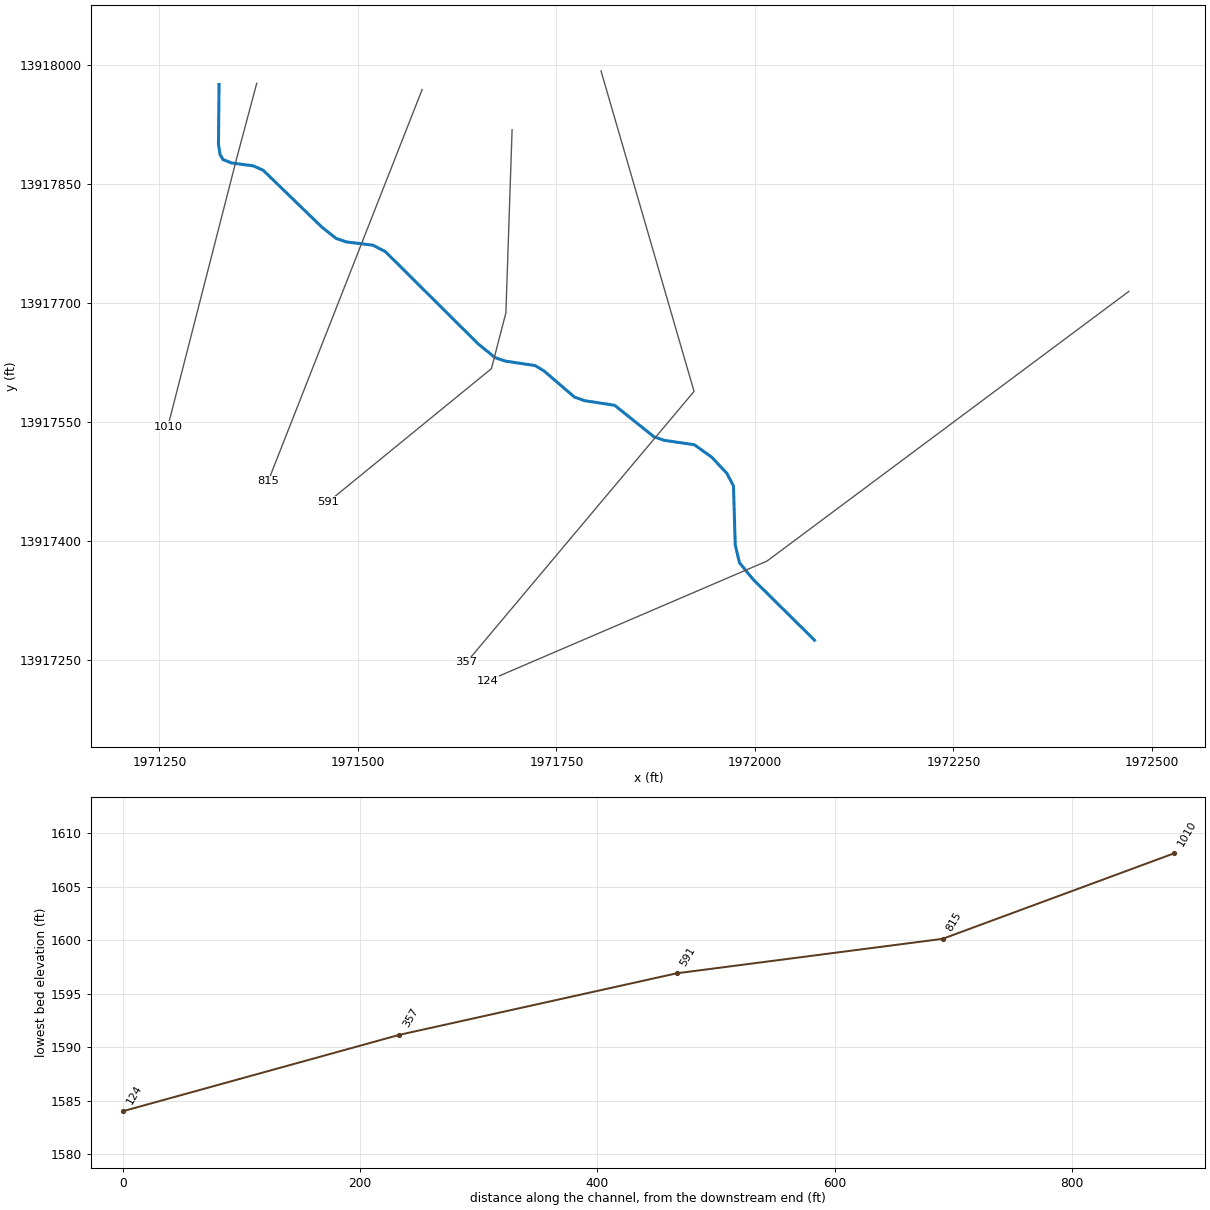
--- Stream0055.prj (project) ---

Proj Title=Stream0055 Base Level Engineering
Current Plan=p01
Default Exp/Contr=0.3,0.1
English Units
Geom File=g01
Flow File=f01
Plan File=p01
BEGIN DESCRIPTION:
Stream0055
END DESCRIPTION:

--- Stream0055.p01 (plan) ---

Plan Title=Multiple Run
Short Identifier=Multiple
Geom File=g01
Flow File=f01
Subcritical Flow
K Sum by GR= 0
Std Step Tol= 0.01
Critical Tol= 0.01
Num of Std Step Trials= 20
Max Error Tol= 0.3
Flow Tol Ratio= 0.001
Split Flow NTrial= 30
Split Flow Tol= 0.02
Split Flow Ratio= 0.02
Log Output Level= 0
Friction Slope Method= 1
Unsteady Friction Slope Method= 2
Unsteady Bridges Friction Slope Method= 1
Parabolic Critical Depth
Global Vel Dist=  1 , 1 , 1
Global Log Level= 0
CheckData=True
Encroach Param= -1, 0, 0, 0
BEGIN DESCRIPTION:
Multiple Run
END DESCRIPTION:

--- Stream0055.f01 (steady flow) ---

Flow Title=Multiple
Number of Profiles=7
Profile Names=10-year,25-year,50-year,1pct_min,100-year,1pct_plu,500-year
River Rch & RM= Stream0055,Reach-1,1010
     179     272     352     222     444     886     696
Boundary for River Rch & Prof#=Stream0055,Reach-1,1
Up Type=0
Dn Type=3
Dn Slope=0.005
Boundary for River Rch & Prof#=Stream0055,Reach-1,2
Up Type=0
Dn Type=3
Dn Slope=0.005
Boundary for River Rch & Prof#=Stream0055,Reach-1,3
Up Type=0
Dn Type=3
Dn Slope=0.005
Boundary for River Rch & Prof#=Stream0055,Reach-1,4
Up Type=0
Dn Type=3
Dn Slope=0.005
Boundary for River Rch & Prof#=Stream0055,Reach-1,5
Up Type=0
Dn Type=3
Dn Slope=0.005
Boundary for River Rch & Prof#=Stream0055,Reach-1,6
Up Type=0
Dn Type=3
Dn Slope=0.005
Boundary for River Rch & Prof#=Stream0055,Reach-1,7
Up Type=0
Dn Type=3
Dn Slope=0.005

--- Stream0055.g01 (geometry) ---

Geom Title=Existing Conditions

River Reach=Stream0055,Reach-1
Reach XY= 30
      1971325.00     13917975.00      1971324.27     13917899.44
      1971326.33     13917886.58      1971330.00     13917880.31
      1971340.73     13917876.06      1971368.52     13917872.34
      1971380.73     13917866.72      1971454.93     13917794.83
      1971472.72     13917780.87      1971485.64     13917776.55
      1971518.95     13917772.47      1971534.68     13917764.22
      1971651.53     13917648.01      1971672.70     13917630.83
      1971685.62     13917626.50      1971723.26     13917620.81
      1971734.54     13917613.90      1971772.80     13917581.08
      1971785.69     13917576.65      1971823.28     13917570.84
      1971872.84     13917531.12      1971885.75     13917526.72
      1971923.61     13917521.15      1971945.57     13917505.42
      1971964.62     13917485.11      1971972.92     13917469.29
      1971975.13     13917395.06      1971980.46     13917372.55
      1971997.77     13917351.43      1972075.00     13917275.00

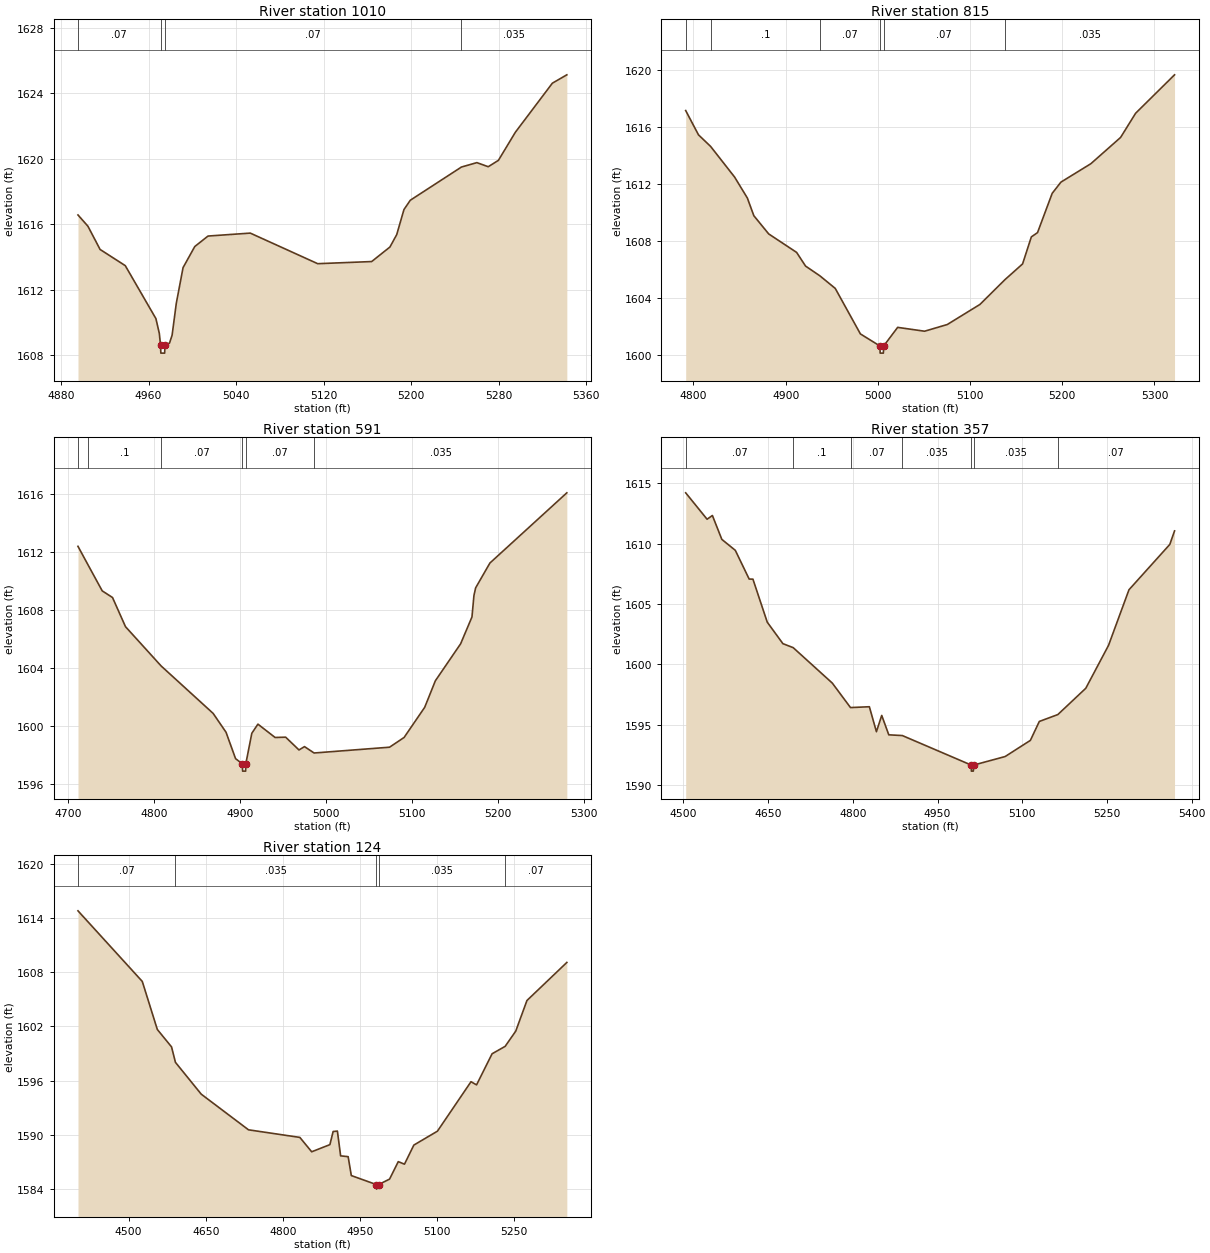
Type RM Length L Ch R = 1,1010,195,195,195
BEGIN DESCRIPTION:
Stream0055 1.0
END DESCRIPTION:
XS GIS Cut Line= 3
      1971372.48     13917976.36      1971347.75     13917883.93
      1971260.50     13917544.04
#Sta/Elev= 30
  4895.5 1616.56  4904.6 1615.87  4915.7 1614.45  4938.7 1613.46  4966.7 1610.22
  4969.8 1609.32  4970.9 1608.61  4971.2 1608.11  4974.7 1608.11  4974.9 1608.61
  4979.1 1608.72  4981.5 1609.21  4985.3 1611.15  4991.5 1613.34  5002.2 1614.63
  5014.3 1615.27  5052.9 1615.45  5114.5 1613.58  5163.8 1613.71  5180.5 1614.60
  5186.7 1615.36  5193.3 1616.89  5199.1 1617.46  5245.8 1619.49  5259.9 1619.76
  5270.3 1619.51  5279.6 1619.90  5295.1 1621.62  5328.9 1624.62  5342.1 1625.13
#Mann=4,-1,0
  4895.5    0.07       0  4970.9    0.05       0  4974.9    0.07       0
  5245.8   0.035       0
Bank Sta=4970.9,4974.9
Exp/Cntr=0.3,0.1

Type RM Length L Ch R = 1,815,224,224,224
BEGIN DESCRIPTION:
Stream0055 2.0
END DESCRIPTION:
XS GIS Cut Line= 2
      1971580.81     13917968.54      1971386.82     13917475.10
#Sta/Elev= 30
  4791.6 1617.17  4805.5 1615.46  4818.6 1614.65  4844.6 1612.50  4858.5 1611.02
  4865.5 1609.78  4881.6 1608.50  4911.9 1607.20  4921.6 1606.24  4937.2 1605.55
  4953.8 1604.67  4981.1 1601.47  5002.3 1600.62  5002.5 1600.12  5006.0 1600.12
  5006.3 1600.62  5021.5 1601.93  5050.7 1601.66  5075.3 1602.13  5110.7 1603.54
  5137.8 1605.28  5157.0 1606.39  5166.5 1608.29  5173.2 1608.59  5189.1 1611.35
  5198.6 1612.14  5231.0 1613.43  5263.3 1615.28  5279.6 1616.98  5321.8 1619.68
#Mann=6,-1,0
  4791.6    0.07       0  4818.6     0.1       0  4937.2    0.07       0
  5002.3    0.05       0  5006.3    0.07       0  5137.8   0.035       0
Bank Sta=5002.3,5006.3
Exp/Cntr=0.3,0.1

Type RM Length L Ch R = 1,591,234,234,234
BEGIN DESCRIPTION:
Stream0055 3.0
END DESCRIPTION:
XS GIS Cut Line= 4
      1971694.10     13917917.81      1971686.29     13917687.31
      1971668.06     13917617.00      1971462.30     13917449.00
#Sta/Elev= 30
  4711.6 1612.40  4723.5 1611.10  4739.8 1609.33  4751.8 1608.87  4766.9 1606.86
  4808.4 1604.15  4868.9 1600.88  4883.9 1599.58  4895.0 1597.76  4902.9 1597.40
  4903.2 1596.90  4906.7 1596.90  4906.9 1597.40  4913.9 1599.51  4921.0 1600.14
  4941.0 1599.22  4953.3 1599.24  4968.8 1598.36  4975.2 1598.59  4986.4 1598.15
  5074.2 1598.55  5091.1 1599.22  5115.1 1601.30  5127.5 1603.13  5156.9 1605.68
  5170.1 1607.53  5172.4 1609.01  5174.4 1609.54  5191.0 1611.25  5280.5 1616.09
#Mann=6,-1,0
  4711.6    0.07       0  4723.5     0.1       0  4808.4    0.07       0
  4902.9   0.035       0  4906.9    0.07       0  4986.4   0.035       0
Bank Sta=4902.9,4906.9
Exp/Cntr=0.3,0.1

Type RM Length L Ch R = 1,357,233,233,233
BEGIN DESCRIPTION:
Stream0055 4.0
END DESCRIPTION:
XS GIS Cut Line= 3
      1971806.09     13917991.98      1971923.27     13917588.35
      1971636.78     13917247.17
#Sta/Elev= 30
  4503.9 1614.22  4541.8 1612.03  4551.2 1612.34  4567.9 1610.36  4591.8 1609.45
  4616.3 1607.07  4623.0 1607.06  4648.4 1603.49  4676.1 1601.71  4694.3 1601.38
  4763.6 1598.44  4795.8 1596.41  4829.2 1596.48  4841.7 1594.41  4851.1 1595.76
  4863.6 1594.15  4887.6 1594.09  5009.7 1591.64  5009.9 1591.14  5013.4 1591.14
  5013.7 1591.64  5069.7 1592.35  5114.4 1593.69  5130.2 1595.26  5163.0 1595.83
  5212.5 1598.01  5252.8 1601.57  5289.0 1606.18  5361.3 1609.94  5369.7 1611.06
#Mann=7,-1,0
  4503.9    0.07       0  4694.3     0.1       0  4795.8    0.07       0
  4887.6   0.035       0  5009.7   0.035       0  5013.7   0.035       0
  5163.0    0.07       0
Bank Sta=5009.7,5013.7
Exp/Cntr=0.3,0.1

Type RM Length L Ch R = 1,124,0,0,0
BEGIN DESCRIPTION:
Stream0055 T
END DESCRIPTION:
XS GIS Cut Line= 3
      1972470.93     13917714.31      1972015.17     13917374.66
      1971663.66     13917223.85
#Sta/Elev= 30
  4401.4 1614.78  4526.5 1606.97  4555.7 1601.66  4583.4 1599.73  4591.0 1598.02
  4641.2 1594.50  4733.1 1590.56  4833.0 1589.72  4856.0 1588.13  4891.4 1588.92
  4897.7 1590.37  4906.0 1590.42  4912.3 1587.68  4926.9 1587.59  4933.1 1585.50
  4982.0 1584.50  4982.2 1584.00  4986.0 1584.50  5007.5 1585.11  5024.4 1587.04
  5036.5 1586.76  5054.7 1588.87  5100.6 1590.41  5165.9 1595.88  5176.7 1595.53
  5206.9 1598.97  5232.3 1599.79  5252.9 1601.47  5274.7 1604.86  5352.3 1609.07
#Mann=5,-1,0
  4401.4    0.07       0  4591.0   0.035       0  4982.0   0.035       0
  4986.0   0.035       0  5232.3    0.07       0
Bank Sta=4982,4986
Exp/Cntr=0.3,0.1

Chan Stop Cuts=-1