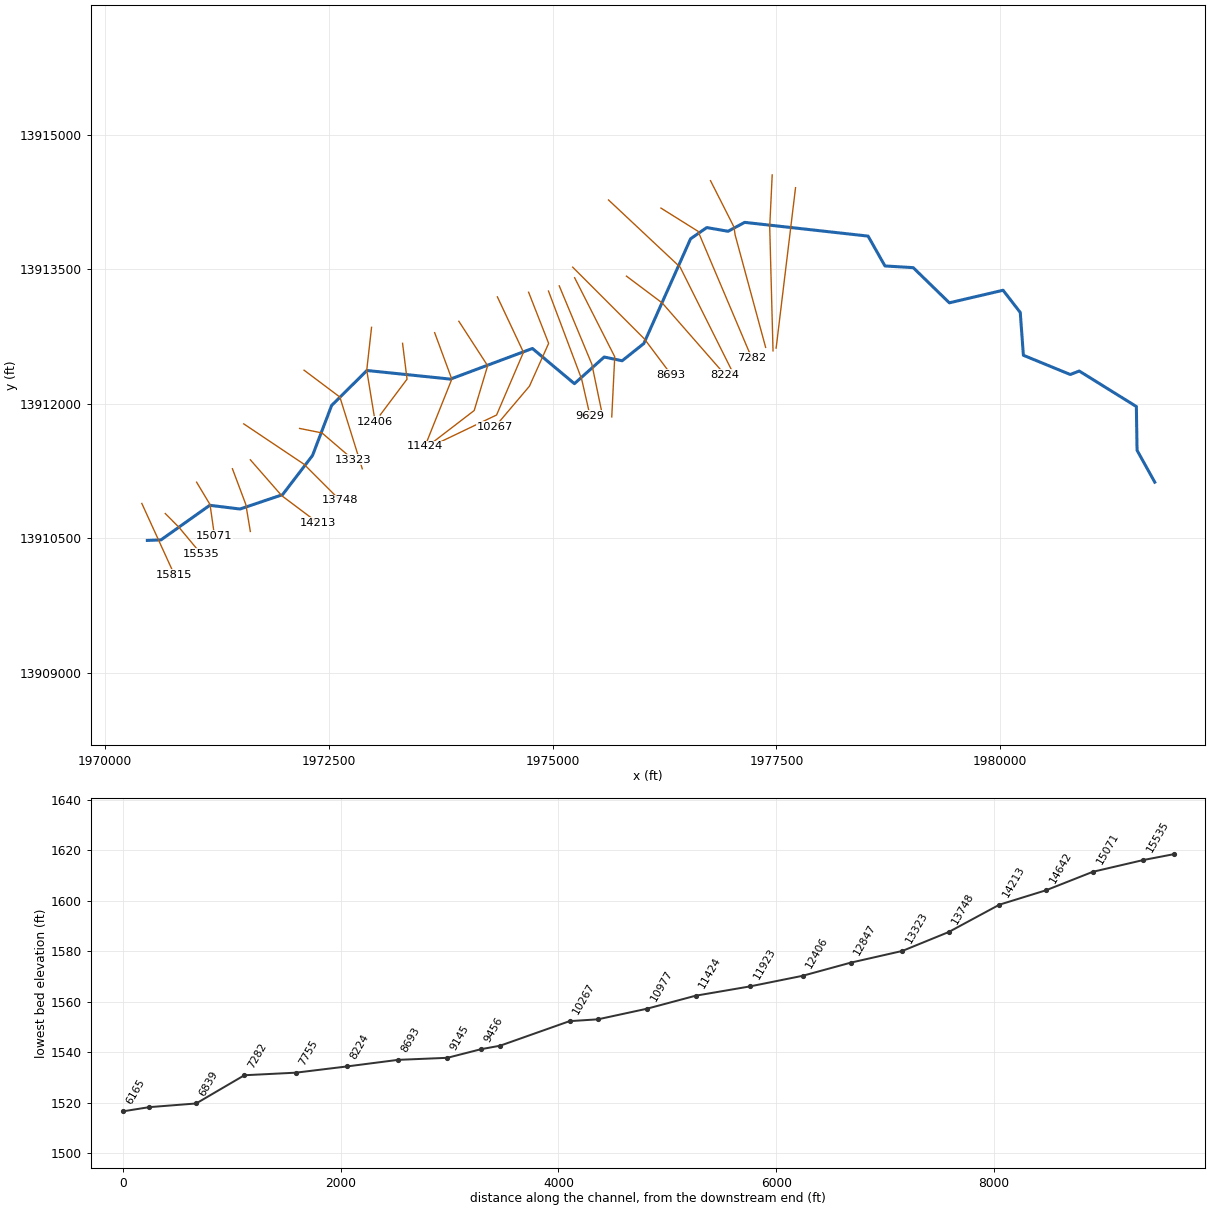
--- Stream0056.prj (project) ---

Proj Title=Stream0056 Base Level Engineering
Current Plan=p01
Default Exp/Contr=0.3,0.1
English Units
Geom File=g01
Flow File=f01
Plan File=p01
Y Axis Title=Elevation
X Axis Title(PF)=Main Channel Distance
X Axis Title(XS)=Station
BEGIN DESCRIPTION:
Stream0056
END DESCRIPTION:
DSS Export Rating Curves= 0
DSS Export Rating Curve Sorted= 0
DSS Export Volume Flow Curves= 0
DXF OffsetX= 0
DXF OffsetY= 0
DXF ScaleX= 1
DXF ScaleY= 10

--- Stream0056.p01 (plan) ---

Plan Title=Multiple Run
Short Identifier=Multiple
Geom File=g01
Flow File=f01
Subcritical Flow
K Sum by GR= 0
Std Step Tol= 0.01
Critical Tol= 0.01
Num of Std Step Trials= 20
Max Error Tol= 0.3
Flow Tol Ratio= 0.001
Split Flow NTrial= 30
Split Flow Tol= 0.02
Split Flow Ratio= 0.02
Log Output Level= 0
Friction Slope Method= 1
Unsteady Friction Slope Method= 2
Unsteady Bridges Friction Slope Method= 1
Parabolic Critical Depth
Global Vel Dist=  1 , 1 , 1
Global Log Level= 0
CheckData=True
Encroach Param= -1, 0, 0, 0
BEGIN DESCRIPTION:
Multiple Run
END DESCRIPTION:

--- Stream0056.f01 (steady flow) ---

Flow Title=Multiple
Program Version=4.10
Number of Profiles= 7
Profile Names=10-year,25-year,50-year,1pct_min,100-year,1pct_plu,500-year
River Rch & RM=Stream0056,Reach-1         ,15815
    1323    2306    3266    2242    4474    8926    8312
River Rch & RM=Stream0056,Reach-1         ,14213
    1489    2614    3720    2566    5121   10217    9629
River Rch & RM=Stream0056,Reach-1         ,9629
    1854    3280    4692    3249    6483   12935   12288
River Rch & RM=Stream0056,Reach-1         ,4572
    2012    3563    5100    3532    7047   14061   13361
Boundary for River Rch & Prof#=Stream0056,Reach-1         , 1
Up Type= 0
Dn Type= 3
Dn Slope=0.01
Boundary for River Rch & Prof#=Stream0056,Reach-1         , 2
Up Type= 0
Dn Type= 3
Dn Slope=0.01
Boundary for River Rch & Prof#=Stream0056,Reach-1         , 3
Up Type= 0
Dn Type= 3
Dn Slope=0.01
Boundary for River Rch & Prof#=Stream0056,Reach-1         , 4
Up Type= 0
Dn Type= 3
Dn Slope=0.01
Boundary for River Rch & Prof#=Stream0056,Reach-1         , 5
Up Type= 0
Dn Type= 3
Dn Slope=0.01
Boundary for River Rch & Prof#=Stream0056,Reach-1         , 6
Up Type= 0
Dn Type= 3
Dn Slope=0.01
Boundary for River Rch & Prof#=Stream0056,Reach-1         , 7
Up Type= 0
Dn Type= 3
Dn Slope=0.01
DSS Import GetInterval= 0
DSS Import GetPeak= 0
DSS Import FillOption= 0

--- Stream0056.g01 (geometry) ---

Geom Title=Existing Conditions
Program Version=4.10

River Reach=Stream0056      ,Reach-1
Reach XY= 30
        1970475.       13910475.      1970627.29      13910480.8
      1971171.68     13910866.96      1971509.78     13910825.52
      1971984.82      13910985.5      1972319.28     13911422.66
      1972532.86     13911981.17      1972926.72     13912371.66
      1973859.79     13912275.51      1974775.01     13912617.47
      1975244.17     13912224.56      1975576.63     13912521.87
      1975777.42     13912480.41      1976019.18     13912672.69
      1976541.44     13913841.79      1976721.68     13913966.96
      1976959.79     13913925.51      1977145.03     13914024.94
      1978523.75     13913871.55      1978711.76     13913538.59
      1979027.45     13913519.55      1979430.85     13913127.06
      1980031.21      13913267.2      1980222.93     13913019.14
      1980257.85     13912541.45      1980781.13     13912326.86
      1980881.61     13912365.57      1981519.42     13911969.41
      1981527.24     13911480.93        1981725.       13911125.

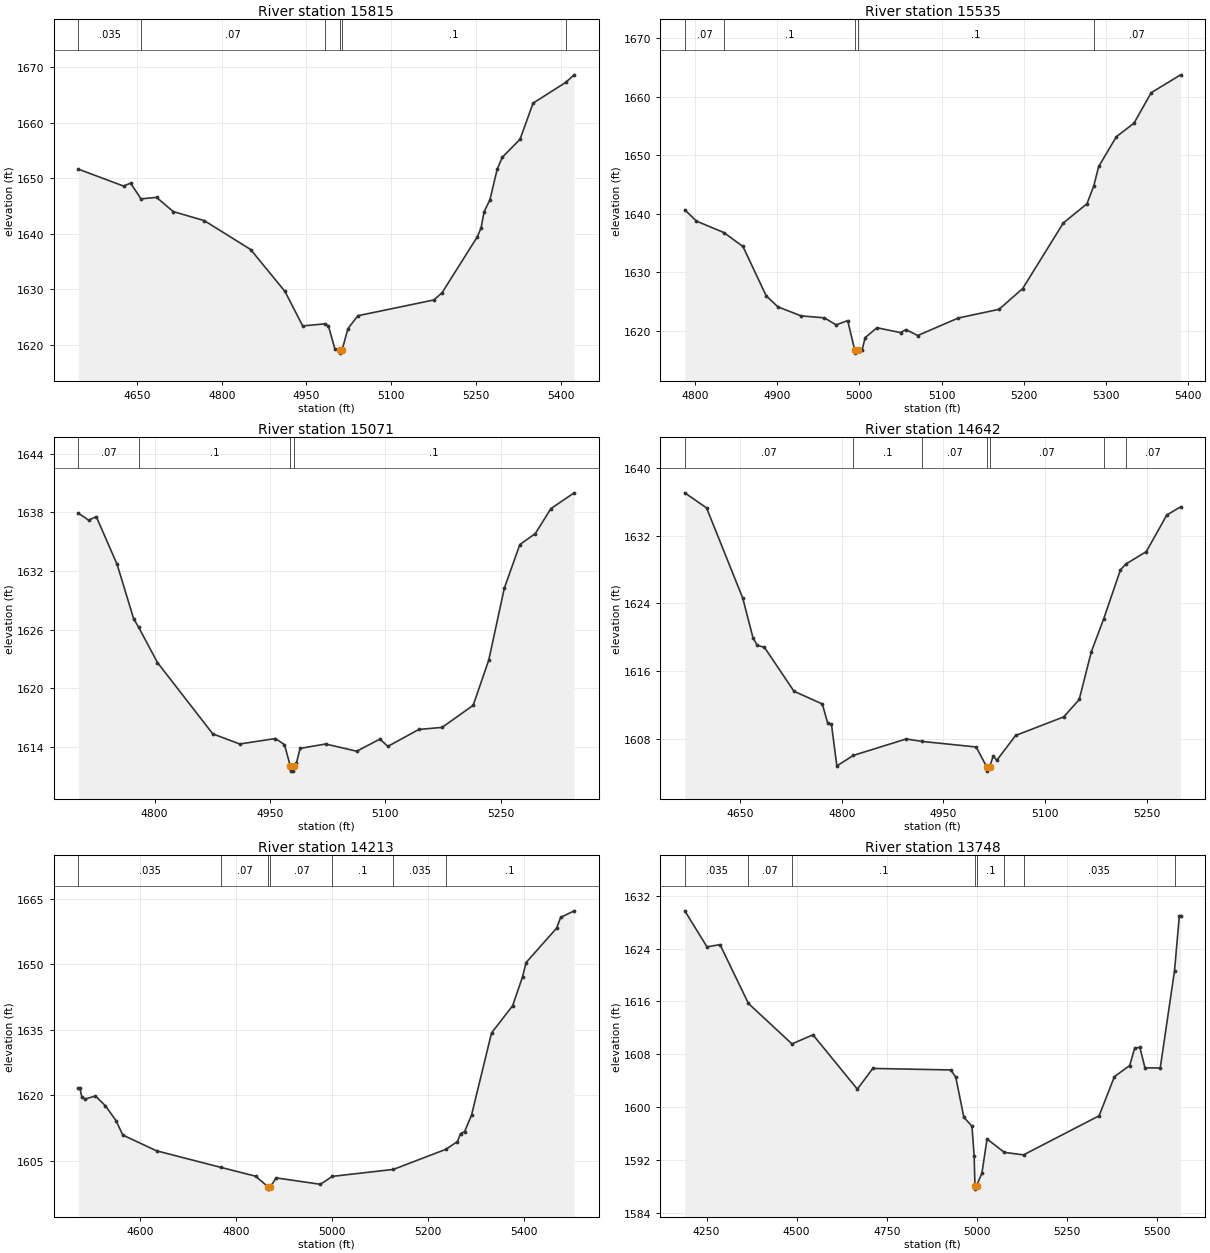
Type RM Length L Ch R = 1 ,15815   ,280,280,280
BEGIN DESCRIPTION:
Stream0056 21.0
END DESCRIPTION:
XS GIS Cut Line= 2
       1970413.2     13910887.81      1970778.17     13910089.26
#Sta/Elev= 30
  4546.1 1651.62  4626.2 1648.57  4638.6  1649.1    4657 1646.27  4684.7 1646.53
  4714.1 1643.98  4769.1 1642.35  4851.3 1637.14    4912  1629.6  4943.4 1623.39
  4982.7 1623.76    4989 1623.39  5000.5 1619.21    5009 1618.99  5009.2 1618.49
    5013 1618.99  5023.5  1622.9    5041 1625.22  5175.9 1628.07  5190.2 1629.37
  5252.9 1639.48  5259.2 1641.03  5264.7 1643.96  5274.9 1646.08  5287.8  1651.6
  5296.8 1653.75  5328.3    1657  5351.3  1663.5  5409.2 1667.24  5424.1  1668.6
#Mann= 6 ,-1 , 0
  4546.1    .035       0    4657     .07       0  4982.7      .1       0
    5009     .05       0    5013      .1       0  5409.2     .07       0
Bank Sta=5009,5013
XS Rating Curve= 0 ,0
Exp/Cntr=0.3,0.1

Type RM Length L Ch R = 1 ,15535   ,464,464,464
BEGIN DESCRIPTION:
Stream0056 20.0
END DESCRIPTION:
XS GIS Cut Line= 3
      1970674.99     13910775.01        1970825.       13910625.
      1971075.02     13910324.97
#Sta/Elev= 30
  4787.9 1640.67  4802.1 1638.74  4835.6 1636.77  4858.6  1634.4  4886.9 1625.95
  4901.1 1624.08  4929.3 1622.54  4957.6  1622.2  4971.8    1621  4985.9 1621.73
  4994.5 1616.67  4994.7 1616.17  4998.6 1616.67  5003.3 1616.67  5007.2 1618.83
  5021.5 1620.51  5050.2 1619.68  5056.7  1620.2    5071 1619.18  5120.5 1622.18
  5169.9 1623.66  5198.6 1627.21    5248 1638.42  5276.7  1641.7    5285 1644.74
    5291 1648.08  5312.5 1653.17  5333.9 1655.48  5354.8 1660.69  5390.6 1663.75
#Mann= 5 ,-1 , 0
  4787.9     .07       0  4835.6      .1       0  4994.5     .05       0
  4998.6      .1       0    5285     .07       0
Bank Sta=4994.5,4998.6
XS Rating Curve= 0 ,0
Exp/Cntr=0.3,0.1

Type RM Length L Ch R = 1 ,15071   ,429,429,429
BEGIN DESCRIPTION:
Stream0056 19.0
END DESCRIPTION:
XS GIS Cut Line= 3
      1971025.02     13911124.97        1971175.       13910875.
        1971225.     13910524.97
#Sta/Elev= 30
  4700.7 1637.93  4714.3  1637.2    4724 1637.58  4751.2 1632.67  4772.6 1627.13
    4779 1626.26  4803.7 1622.62  4875.6 1615.32  4910.6 1614.28  4957.2 1614.84
  4968.9 1614.21  4976.6    1612  4976.8  1611.5  4980.4  1611.5  4980.7    1612
  4984.4 1612.32  4989.3 1613.83  5022.5 1614.28  5062.9 1613.54  5093.2 1614.79
  5103.3 1614.03  5143.7 1615.77    5174 1615.98  5214.4 1618.24  5234.7 1622.88
  5254.9 1630.23  5275.1 1634.71  5295.3 1635.84  5315.5 1638.39  5345.8 1640.01
#Mann= 4 ,-1 , 0
  4700.7     .07       0    4779      .1       0  4976.6     .05       0
  4980.7      .1       0
Bank Sta=4976.6,4980.7
XS Rating Curve= 0 ,0
Exp/Cntr=0.3,0.1

Type RM Length L Ch R = 1 ,14642   ,429,429,429
BEGIN DESCRIPTION:
Stream0056 18.0
END DESCRIPTION:
XS GIS Cut Line= 3
      1971424.99     13911275.02        1971575.       13910875.
      1971625.01     13910574.96
#Sta/Elev= 30
  4568.5 1637.06  4600.6 1635.28    4654 1624.62  4669.1 1619.94  4675.3 1619.06
    4686 1618.81  4729.6 1613.62  4771.4 1612.12  4779.4 1609.83  4784.8 1609.75
  4792.8  1604.8  4817.2 1606.05  4895.1 1607.99  4918.3  1607.7  4998.3 1607.04
  5013.9 1604.69  5014.2 1604.19    5018 1604.69  5023.6 1605.98  5028.7 1605.47
  5056.5  1608.4  5127.5  1610.6  5150.3 1612.65  5168.1 1618.27  5186.6 1622.21
  5211.1 1627.96  5218.9 1628.64  5249.2 1630.11  5279.6 1634.45  5299.9  1635.4
#Mann= 7 ,-1 , 0
  4568.5     .07       0  4817.2      .1       0  4918.3     .07       0
  5013.9     .05       0    5018     .07       0  5186.6      .1       0
  5218.9     .07       0
Bank Sta=5013.9,5018
XS Rating Curve= 0 ,0
Exp/Cntr=0.3,0.1

Type RM Length L Ch R = 1 ,14213   ,465,465,465
BEGIN DESCRIPTION:
Stream0056 17.0
END DESCRIPTION:
XS GIS Cut Line= 3
      1971624.99     13911375.01        1971975.       13910975.
      1972374.99     13910675.01
#Sta/Elev= 30
  4472.3 1621.63  4475.6 1621.63  4479.4 1619.66  4486.1 1619.13  4507.9 1619.82
  4528.8 1617.56  4550.6  1614.2  4564.8 1610.86  4635.1 1607.25  4769.5 1603.43
    4841 1601.43  4867.3 1598.96  4867.6 1598.46  4871.7 1598.96  4883.8 1601.04
  4975.8 1599.57  5000.8 1601.39  5127.6 1602.98    5237  1607.6  5261.1 1609.38
  5267.4 1611.22  5275.7 1611.62  5290.3 1615.43  5331.9 1634.29  5375.7 1640.53
  5396.5 1647.19  5403.8 1650.45  5467.4 1658.35  5475.7  1660.8  5503.8 1662.31
#Mann= 7 ,-1 , 0
  4472.3    .035       0  4769.5     .07       0  4867.3     .05       0
  4871.7     .07       0  5000.8      .1       0  5127.6    .035       0
    5237      .1       0
Bank Sta=4867.3,4871.7
XS Rating Curve= 0 ,0
Exp/Cntr=0.3,0.1

Type RM Length L Ch R = 1 ,13748   ,425,425,425
BEGIN DESCRIPTION:
Stream0056 16.0
END DESCRIPTION:
XS GIS Cut Line= 3
      1971551.29     13911775.98        1972225.       13911325.
      1972624.99     13910925.01
#Sta/Elev= 30
  4189.5 1629.71  4251.1 1624.26  4287.2  1624.6  4366.2  1615.7  4486.9 1609.59
  4545.4 1610.96  4668.5 1602.75  4711.4 1605.88    4928 1605.65  4941.7 1604.56
  4964.1 1598.51  4986.7 1597.14  4992.7 1592.69    4995 1588.13  4995.3 1587.63
  4999.5 1588.13  5014.4 1590.08  5028.5 1595.22  5076.4 1593.19  5129.8 1592.81
  5339.6 1598.72  5382.1 1604.64  5424.5 1606.32  5438.6 1608.98  5452.8 1609.05
  5466.9 1605.97  5509.3 1605.95  5548.9 1620.63  5562.4 1628.98  5565.9 1628.98
#Mann= 8 ,-1 , 0
  4189.5    .035       0  4366.2     .07       0  4486.9      .1       0
    4995     .05       0  4999.5      .1       0  5076.4     .07       0
  5129.8    .035       0  5548.9      .1       0
Bank Sta=4995,4999.5
XS Rating Curve= 0 ,0
Exp/Cntr=0.3,0.1

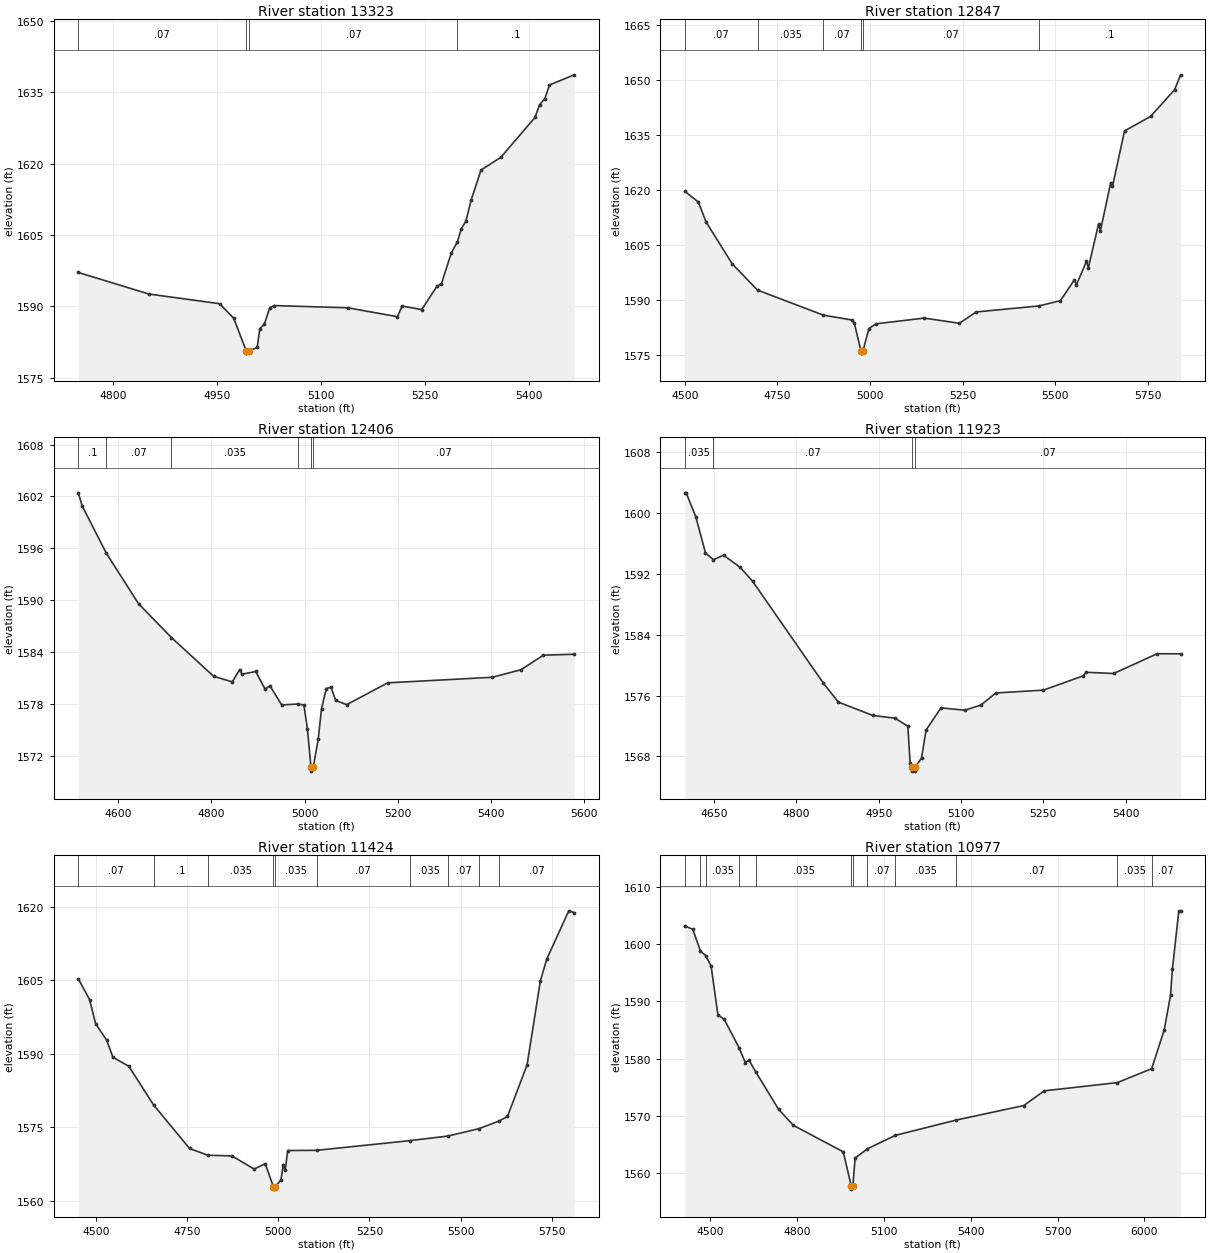
Type RM Length L Ch R = 1 ,13323   ,476,476,476
BEGIN DESCRIPTION:
Stream0056 15.0
END DESCRIPTION:
XS GIS Cut Line= 3
      1972174.97     13911725.01        1972425.       13911675.
      1972775.03     13911374.97
#Sta/Elev= 30
  4749.3 1597.09  4851.3 1592.56  4953.3 1590.53  4973.7 1587.46  4991.7 1580.64
  4992.1 1580.14  4996.4 1580.64  5007.6 1581.33  5011.4 1585.28    5018 1586.26
  5025.7 1589.69  5032.3 1590.14  5138.7 1589.66  5210.1  1587.8  5216.7 1590.03
  5245.2  1589.3  5267.1 1594.17  5273.7 1594.76    5288 1601.25  5296.7 1603.52
  5302.3 1606.31  5308.9 1607.86  5316.5 1612.29  5330.8 1618.62  5359.3 1621.29
  5408.7 1629.67  5415.3 1632.34    5423 1633.65  5429.6  1636.5  5465.3 1638.64
#Mann= 4 ,-1 , 0
  4749.3     .07       0  4991.7     .05       0  4996.4     .07       0
  5296.7      .1       0
Bank Sta=4991.7,4996.4
XS Rating Curve= 0 ,0
Exp/Cntr=0.3,0.1

Type RM Length L Ch R = 1 ,12847   ,441,441,441
BEGIN DESCRIPTION:
Stream0056 14.0
END DESCRIPTION:
XS GIS Cut Line= 3
      1972224.99     13912375.01        1972625.       13912075.
      1972875.01     13911274.96
#Sta/Elev= 30
    4500 1619.63  4536.5 1616.73  4557.3 1611.29  4628.1 1599.81  4696.3 1592.67
  4874.1 1585.83    4950 1584.53  4957.3 1583.79  4975.7 1575.97  4976.1 1575.47
  4980.5 1575.97  4996.9 1582.17  5016.2 1583.47  5146.2 1585.03    5241 1583.62
  5286.6 1586.71  5454.9 1588.34  5513.4 1589.76  5551.6 1595.47  5556.9 1594.09
  5584.1 1600.51  5589.3 1598.82  5616.6 1610.68  5621.8 1608.88  5649.1  1621.8
  5654.3 1620.96  5686.8 1636.11    5757 1640.06  5821.9 1647.35  5838.2 1651.42
#Mann= 6 ,-1 , 0
    4500     .07       0  4696.3    .035       0  4874.1     .07       0
  4975.7     .05       0  4980.5     .07       0  5454.9      .1       0
Bank Sta=4975.7,4980.5
XS Rating Curve= 0 ,0
Exp/Cntr=0.3,0.1

Type RM Length L Ch R = 1 ,12406   ,483,483,483
BEGIN DESCRIPTION:
Stream0056 13.0
END DESCRIPTION:
XS GIS Cut Line= 3
      1972978.71     13912853.35        1972925.       13912375.
      1973018.93     13911800.08
#Sta/Elev= 30
  4514.7 1602.42  4523.1 1600.89  4574.7 1595.45  4643.9 1589.61  4714.5  1585.7
  4804.9 1581.23  4845.1 1580.58  4860.9    1582    4866 1581.47  4895.4 1581.78
  4915.6 1579.72  4925.6 1580.15    4951 1577.92  4985.1 1578.02  4998.6 1577.93
  5006.2 1575.19  5013.8 1570.77  5014.2 1570.27  5018.9 1570.77  5029.3 1573.93
  5036.6 1577.49  5046.7 1579.81  5056.9 1579.96    5067 1578.43  5090.7 1577.95
  5178.4 1580.47  5402.8 1581.11  5464.2 1581.98  5512.8 1583.67  5578.6 1583.77
#Mann= 6 ,-1 , 0
  4514.7      .1       0  4574.7     .07       0  4714.5    .035       0
  4985.1     .07       0  5013.8     .05       0  5018.9     .07       0
Bank Sta=5013.8,5018.9
XS Rating Curve= 0 ,0
Exp/Cntr=0.3,0.1

Type RM Length L Ch R = 1 ,11923   ,499,499,499
BEGIN DESCRIPTION:
Stream0056 12.0
END DESCRIPTION:
XS GIS Cut Line= 3
      1973325.01     13912674.96        1973375.       13912275.
      1973074.98     13911874.98
#Sta/Elev= 30
  4596.9 1602.67  4599.4 1602.67    4617 1599.51  4634.6 1594.76  4649.1 1593.87
  4667.4 1594.47  4697.6 1592.88  4720.3 1591.05  4848.8 1577.69  4876.5 1575.15
  4939.5 1573.39  4979.8 1573.03  5003.1 1571.98  5007.3 1567.16  5010.9 1566.57
  5011.3 1566.07  5015.7 1566.07  5016.1 1566.57  5028.1  1567.8  5036.4 1571.48
  5063.5 1574.39  5107.3 1574.08  5136.4 1574.77  5163.5 1576.35    5250 1576.72
  5321.8 1578.58  5328.1 1579.07  5378.1 1578.91  5457.3 1581.51    5500  1581.5
#Mann= 4 ,-1 , 0
  4596.9    .035       0  4649.1     .07       0  5010.9     .05       0
  5016.1     .07       0
Bank Sta=5010.9,5016.1
XS Rating Curve= 0 ,0
Exp/Cntr=0.3,0.1

Type RM Length L Ch R = 1 ,11424   ,447,447,447
BEGIN DESCRIPTION:
Stream0056 11.0
END DESCRIPTION:
XS GIS Cut Line= 3
      1973683.35     13912793.92        1973875.       13912275.
      1973575.02     13911525.04
#Sta/Elev= 30
  4450.9  1605.3  4481.7 1601.07  4498.3 1596.16  4528.8 1592.77  4545.7 1589.32
  4589.6 1587.45  4657.4 1579.57  4756.1 1570.68  4806.2  1569.3  4872.5 1569.16
  4933.3 1566.48  4963.8 1567.57  4986.3 1562.88  4986.7 1562.38  4991.5 1562.88
  5006.8 1564.24  5013.5 1567.22  5018.9 1566.32  5025.6 1570.26    5105  1570.3
  5359.9 1572.27  5465.8 1573.22  5550.2 1574.72  5606.2 1576.29  5628.8 1577.22
  5682.6 1587.74    5719 1604.87  5736.5 1609.32    5797 1619.19  5811.8 1618.83
#Mann= 10 ,-1 , 0
  4450.9     .07       0  4657.4      .1       0  4806.2    .035       0
  4986.3    .035       0  4991.5    .035       0    5105     .07       0
  5359.9    .035       0  5465.8     .07       0  5550.2    .035       0
  5606.2     .07       0
Bank Sta=4986.3,4991.5
XS Rating Curve= 0 ,0
Exp/Cntr=0.3,0.1

Type RM Length L Ch R = 1 ,10977   ,449,449,449
BEGIN DESCRIPTION:
Stream0056 10.0
END DESCRIPTION:
XS GIS Cut Line= 4
      1973953.66     13912920.88        1974275.       13912425.
        1974125.       13911925.      1973650.16     13911560.52
#Sta/Elev= 30
  4413.4 1603.15  4440.9 1602.59  4467.4  1598.8    4486 1597.96  4504.2 1596.17
  4527.7 1587.65  4549.6 1586.86  4600.9  1581.9  4622.2 1579.32  4634.9 1579.75
    4658 1577.72  4736.9 1571.17  4788.3 1568.35  4960.5 1563.73  4988.1 1557.72
  4988.5 1557.22  4993.4 1557.72  5001.3 1562.64  5043.9 1564.27  5140.4 1566.61
  5350.3 1569.28  5583.4 1571.81  5654.1 1574.38  5906.7 1575.82  6024.9 1578.25
  6068.4 1585.05  6090.1  1591.1  6096.4 1595.59  6118.7 1605.81  6124.9 1605.81
#Mann= 12 ,-1 , 0
  4413.4     .07       0  4467.4      .1       0    4486    .035       0
  4600.9     .07       0    4658    .035       0  4988.1    .035       0
  4993.4    .035       0  5043.9     .07       0  5140.4    .035       0
  5350.3     .07       0  5906.7    .035       0  6024.9     .07       0
Bank Sta=4988.1,4993.4
XS Rating Curve= 0 ,0
Exp/Cntr=0.3,0.1

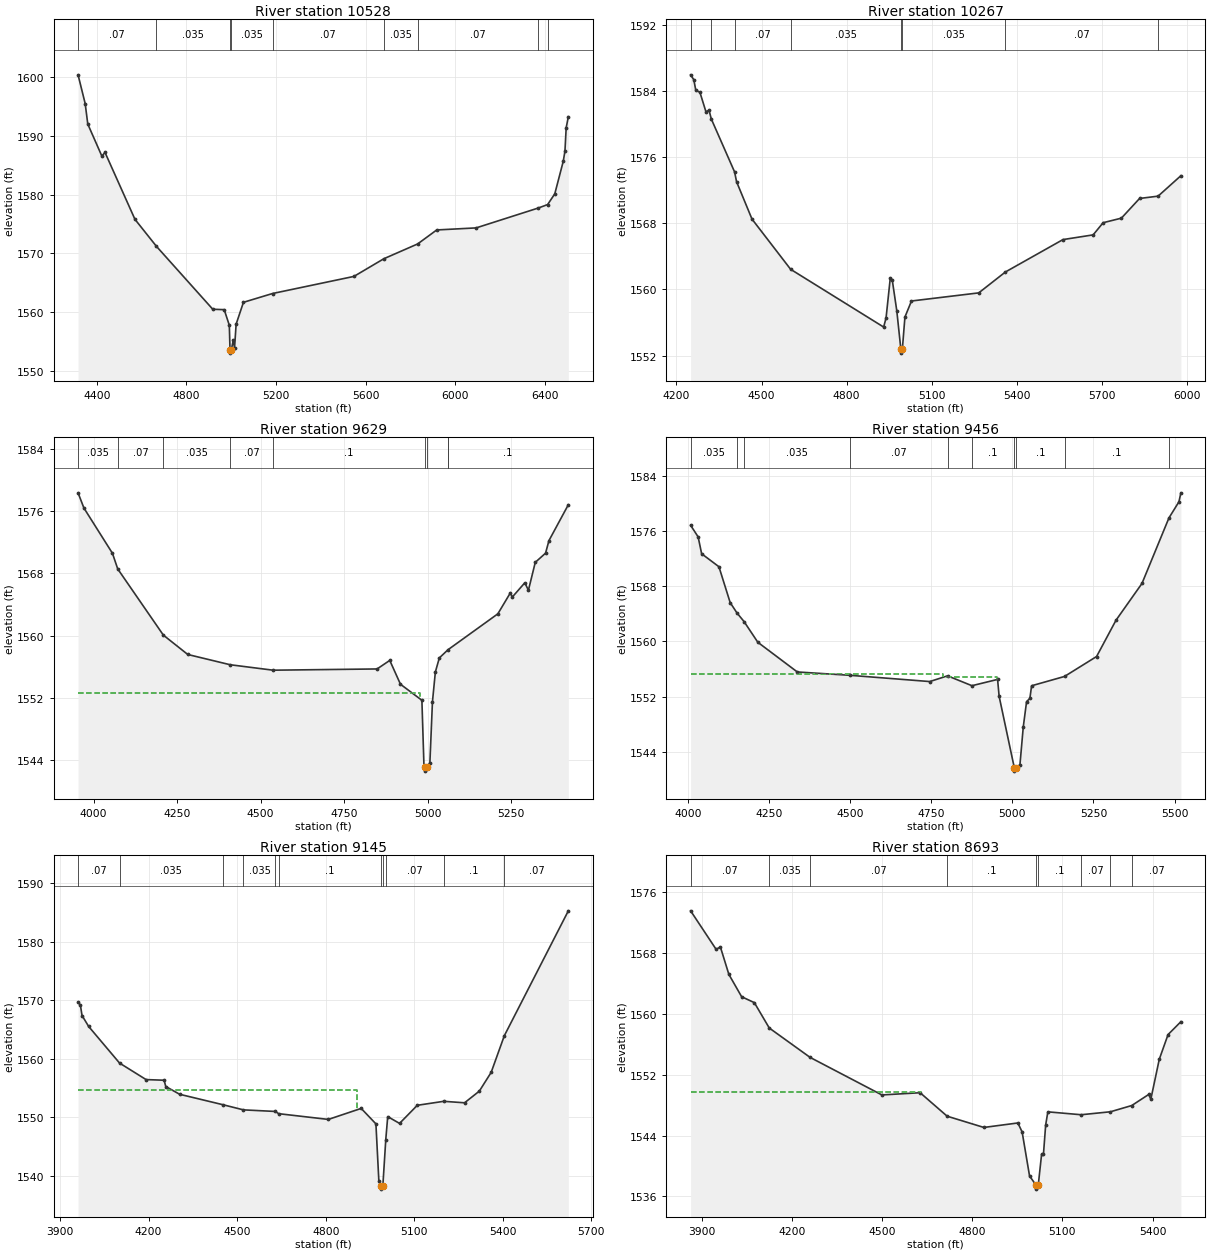
Type RM Length L Ch R = 1 ,10528   ,261,261,261
BEGIN DESCRIPTION:
Stream0056 9.0
END DESCRIPTION:
XS GIS Cut Line= 4
      1974383.67      13913193.8        1974675.       13912575.
        1974375.       13911875.      1973704.46     13911554.33
#Sta/Elev= 30
  4316.1 1600.41  4347.9 1595.52  4359.5 1592.03  4422.3 1586.58  4436.4  1587.2
  4570.1 1575.81  4666.3  1571.2  4917.5  1560.5  4968.6 1560.43  4991.4 1557.77
  4994.6 1553.53    4995 1553.03  4999.9 1553.53  5009.1 1555.26  5014.6 1553.87
  5021.8 1557.96  5054.4 1561.68  5184.4 1563.18  5547.7 1566.09  5681.3  1569.1
  5832.2 1571.62  5917.3    1574  6093.2 1574.35  6370.4 1577.73  6412.4 1578.32
  6444.4 1580.15  6482.1 1585.67  6489.7 1587.39  6495.3  1591.4  6504.9 1593.28
#Mann= 9 ,-1 , 0
  4316.1     .07       0  4666.3    .035       0  4994.6    .035       0
  4999.9    .035       0  5184.4     .07       0  5681.3    .035       0
  5832.2     .07       0  6370.4    .035       0  6412.4     .07       0
Bank Sta=4994.6,4999.9
XS Rating Curve= 0 ,0
Exp/Cntr=0.3,0.1

Type RM Length L Ch R = 1 ,10267   ,638,638,638
BEGIN DESCRIPTION:
Mapping XS d50e522d
END DESCRIPTION:
XS GIS Cut Line= 4
      1974732.57     13913245.38      1974956.35     13912674.27
      1974741.88     13912196.46      1974359.12     13911744.87
#Sta/Elev= 30
    4250 1585.93  4261.2 1585.34  4268.4 1584.04  4282.6 1583.84  4304.1 1581.46
  4314.9 1581.66    4323 1580.59    4405  1574.2  4412.1 1573.01  4466.4  1568.5
  4602.7 1562.43  4930.8 1555.45  4939.3 1556.56    4954 1561.32  4961.2 1561.12
  4977.1 1557.42  4991.4  1552.8  4991.9  1552.3  4996.8  1552.8  5005.8 1556.66
  5028.9  1558.6  5266.1 1559.58  5360.4 1562.11  5563.1 1566.02  5669.6 1566.59
  5704.8 1568.06  5769.2 1568.61  5833.4 1570.99  5898.7 1571.27  5979.1 1573.74
#Mann= 8 ,-1 , 0
    4250     .07       0    4323    .035       0    4405     .07       0
  4602.7    .035       0  4991.4    .035       0  4996.8    .035       0
  5360.4     .07       0  5898.7    .035       0
#XS Ineff= 2 , 0
         4957.04 1559.42
Permanent Ineff=
       F       F
Bank Sta=4991.4,4996.8
XS Rating Curve= 0 ,0
Exp/Cntr=0.3,0.1

Type RM Length L Ch R = 1 ,9629    ,173,173,173
BEGIN DESCRIPTION:
Stream0056 8.0
END DESCRIPTION:
XS GIS Cut Line= 3
       1974954.5      13913258.3        1975325.       13912275.
      1975418.04     13911868.49
#Sta/Elev= 30
  3953.7 1578.35  3971.3 1576.39  4056.6 1570.58  4072.5 1568.56  4209.1 1560.05
  4282.2 1557.56  4409.3 1556.24  4537.6 1555.54    4849  1555.7  4886.9  1556.8
    4919 1553.73  4983.1 1551.67  4989.4 1543.07  4991.3 1543.06  4991.8 1542.56
  4998.1 1543.06    5007 1543.61  5014.7 1551.49  5023.4 1555.31  5035.3 1557.12
  5061.2 1558.17  5210.5 1562.79  5248.3 1565.51  5253.4 1564.93  5291.2 1566.78
    5302 1565.82  5322.5 1569.41  5353.3 1570.59  5363.5 1572.21  5421.5 1576.82
#Mann= 9 ,-1 , 0
  3953.7    .035       0  4072.5     .07       0  4209.1    .035       0
  4409.3     .07       0  4537.6      .1       0  4991.3     .05       0
  4998.1      .1       0  5061.2     .07       0  5061.2      .1       0
#XS Ineff= 2 , 0
         4976.02 1552.61
Permanent Ineff=
       F       F
Bank Sta=4991.3,4998.1
XS Rating Curve= 0 ,0
Exp/Cntr=0.3,0.1

Type RM Length L Ch R = 1 ,9456    ,311,311,311
BEGIN DESCRIPTION:
Mapping XS d21464b6
END DESCRIPTION:
XS GIS Cut Line= 3
      1975074.66     13913316.37      1975438.58     13912442.49
      1975553.73     13911889.07
#Sta/Elev= 30
  4007.8 1576.83    4031 1575.14  4041.8  1572.7  4095.1 1570.82  4129.8 1565.62
  4150.9 1564.11  4172.8 1562.86  4215.1 1559.87  4336.8 1555.57  4498.1 1555.09
  4745.3 1554.18  4800.1 1555.01  4875.3 1553.58  4954.4 1554.49  4959.2 1552.03
  5005.9  1541.7  5006.4  1541.2  5012.7  1541.7  5023.4 1542.15  5033.6  1547.6
  5043.8 1551.27    5054 1551.74  5059.3 1553.57  5160.8 1554.92  5259.7 1557.81
  5319.6 1563.07  5399.7  1568.4  5482.8 1577.89  5513.6 1580.23  5519.7 1581.53
#Mann= 10 ,-1 , 0
  4007.8    .035       0  4150.9     .07       0  4172.8    .035       0
  4498.1     .07       0  4800.1    .035       0  4875.3      .1       0
  5005.9     .05       0  5012.7      .1       0  5160.8      .1       0
  5482.8     .07       0
#XS Ineff= 2 ,-1
  4007.8  4786.8 1555.21 4794.41 4952.65 1554.77
Permanent Ineff=
       F       F
Bank Sta=5005.9,5012.7
XS Rating Curve= 0 ,0
Exp/Cntr=0.3,0.1

Type RM Length L Ch R = 1 ,9145    ,452,452,452
BEGIN DESCRIPTION:
Stream0056 7.0
END DESCRIPTION:
XS GIS Cut Line= 3
       1975246.4     13913407.01      1975694.42     13912524.92
      1975661.19     13911853.79
#Sta/Elev= 30
  3960.9 1569.68  3968.8 1569.18  3974.4 1567.41  3996.8 1565.54  4101.5 1559.29
  4191.4 1556.47  4252.5 1556.36  4258.1 1555.29  4305.2 1553.96  4452.7 1552.17
  4521.3  1551.3  4629.8 1551.03  4640.6 1550.65    4809 1549.67  4920.3 1551.55
  4970.2 1548.91  4980.2 1539.13  4986.8 1538.27  4987.3 1537.77  4993.6 1538.27
  5003.6 1546.22  5010.2 1550.15  5050.3 1548.99  5110.4 1552.08  5199.8 1552.76
  5270.6 1552.51  5320.6  1554.5  5360.7  1557.7  5405.4 1563.97  5622.2 1585.28
#Mann= 11 ,-1 , 0
  3960.9     .07       0  4101.5    .035       0  4452.7     .07       0
  4521.3    .035       0  4629.8     .07       0  4640.6      .1       0
  4986.8     .05       0  4993.6      .1       0  5003.6     .07       0
  5199.8      .1       0  5405.4     .07       0
#XS Ineff= 2 , 0
         4906.89 1554.67 5012.32         1550.02
Permanent Ineff=
       F       F
Bank Sta=4986.8,4993.6
XS Rating Curve= 0 ,0
Exp/Cntr=0.3,0.1

Type RM Length L Ch R = 1 ,8693    ,469,469,469
BEGIN DESCRIPTION:
Stream0056 6.0
END DESCRIPTION:
XS GIS Cut Line= 3
        1975225.       13913525.        1976025.       13912725.
      1976325.02     13912324.98
#Sta/Elev= 30
  3863.1 1573.51    3948 1568.45  3962.1 1568.77  3990.4 1565.16  4032.8 1562.23
  4075.2 1561.45  4124.8 1558.12  4260.7 1554.26  4499.5 1549.33  4626.8 1549.62
  4716.6 1546.54  4838.9 1545.06    4952 1545.65  4966.2 1544.47  4990.9 1538.69
  5012.9 1537.46  5013.4 1536.96  5019.8 1537.46  5030.9 1541.51  5037.2 1541.56
  5044.5 1545.38  5051.8 1547.11  5162.7 1546.73  5260.1 1547.12    5331 1547.94
  5387.2 1549.39  5394.5 1548.78  5422.6 1554.02  5451.8 1557.26  5494.5 1558.95
#Mann= 9 ,-1 , 0
  3863.1     .07       0  4124.8    .035       0  4260.7     .07       0
  4716.6      .1       0  5012.9     .05       0  5019.8      .1       0
  5162.7     .07       0  5260.1    .035       0    5331     .07       0
#XS Ineff= 2 , 0
         4628.97 1549.77
Permanent Ineff=
       F       F
Bank Sta=5012.9,5019.8
XS Rating Curve= 0 ,0
Exp/Cntr=0.3,0.1

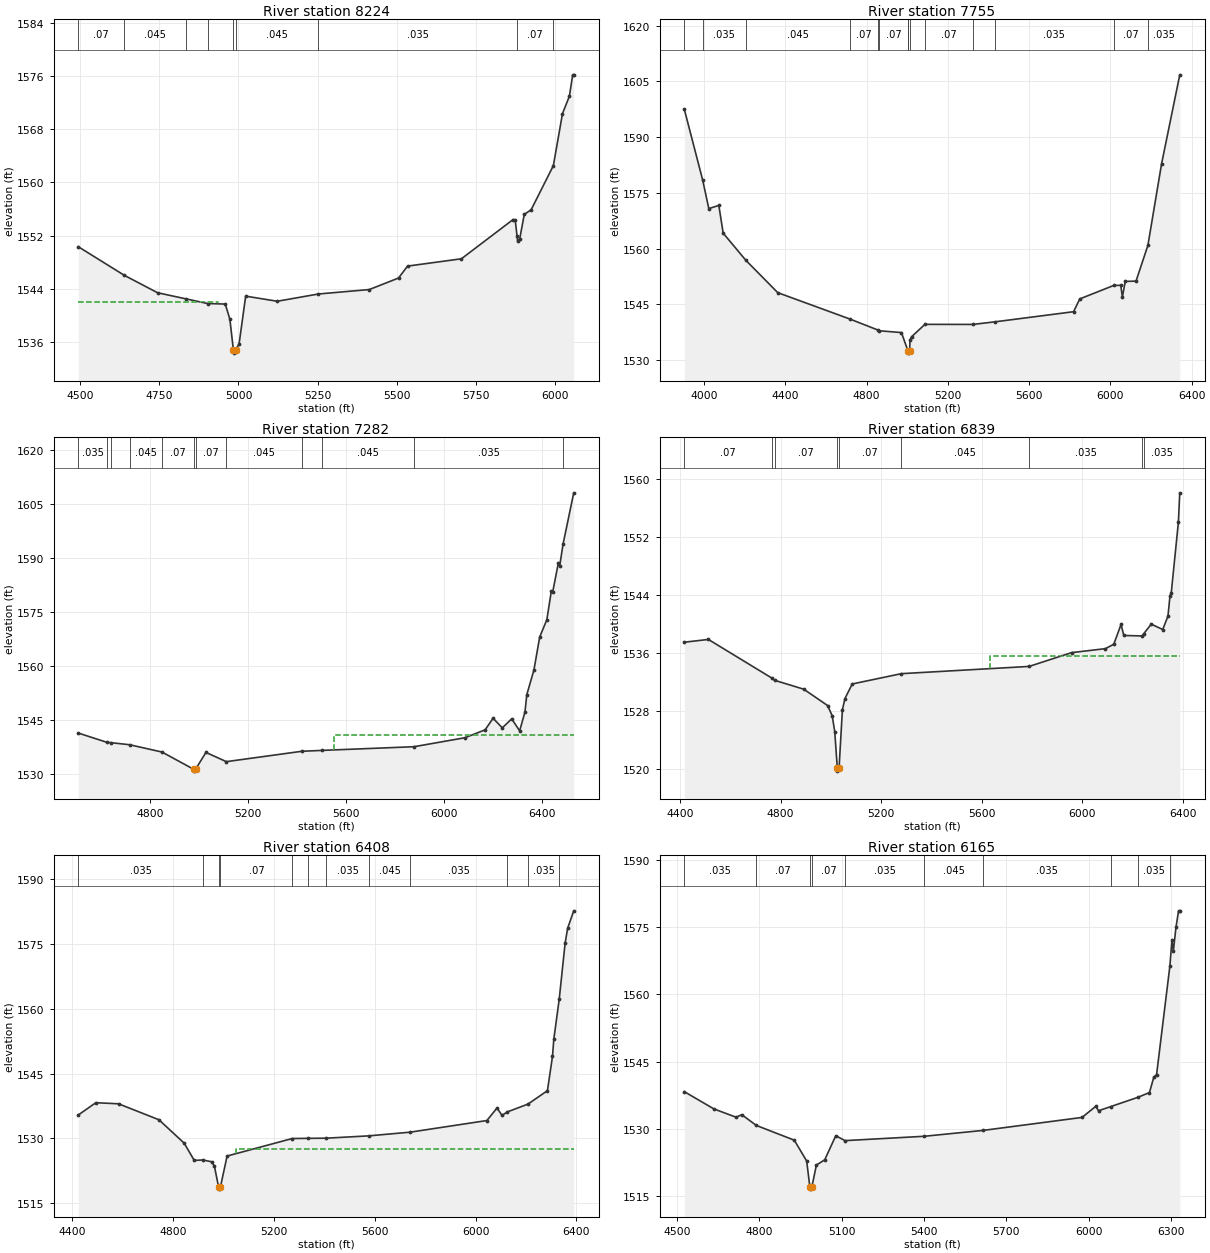
Type RM Length L Ch R = 1 ,8224    ,469,469,469
BEGIN DESCRIPTION:
Stream0056 5.0
END DESCRIPTION:
XS GIS Cut Line= 3
      1975824.97     13913425.02        1976225.       13913125.
      1976924.97     13912325.04
#Sta/Elev= 30
  4494.7 1550.33  4639.7 1546.04  4744.7 1543.42  4834.3  1542.5  4902.5  1541.8
  4958.3 1541.72  4972.9 1539.43  4983.9 1534.85  4984.4 1534.35    4991 1534.85
  5001.9 1535.72  5022.7 1542.91  5122.4 1542.14  5251.9 1543.23  5412.8  1543.9
  5504.9 1545.63  5533.4 1547.42  5703.3 1548.52  5866.5 1554.42  5873.1 1554.34
  5878.8 1551.96  5880.7 1551.16  5887.4 1551.54  5901.6 1555.18  5923.4 1555.89
  5993.4 1562.51  6022.2 1570.32    6044 1572.94  6054.4 1576.15  6057.7 1576.15
#Mann= 9 ,-1 , 0
  4494.7     .07       0  4639.7    .045       0  4834.3     .07       0
  4902.5    .045       0  4983.9     .05       0    4991    .045       0
  5251.9    .035       0  5878.8     .07       0  5993.4    .035       0
#XS Ineff= 2 , 0
         4934.07 1542.08
Permanent Ineff=
       F       F
Bank Sta=4983.9,4991
XS Rating Curve= 0 ,0
Exp/Cntr=0.3,0.1

Type RM Length L Ch R = 1 ,7755    ,473,473,473
BEGIN DESCRIPTION:
Stream0056 4.0
END DESCRIPTION:
XS GIS Cut Line= 3
      1975625.01     13914274.99        1976425.       13913525.
      1977024.99     13912325.01
#Sta/Elev= 30
  3903.4 1597.45  3993.4 1578.48  4023.8 1570.76  4073.1 1571.61  4094.6 1564.15
  4205.9 1556.86  4363.3 1548.14  4716.3 1541.09  4854.8 1538.12  4861.7  1537.9
  4971.9 1537.41  5004.4 1532.39  5004.8 1532.38  5005.3 1531.88    5012 1532.38
    5014  1535.5  5022.3 1536.32  5087.4 1539.62    5323  1539.6  5431.2 1540.29
  5818.9 1543.02  5849.7 1546.47  6016.4 1550.08  6050.9 1550.12  6059.3 1547.02
  6073.3 1551.17  6126.4 1551.25  6184.8 1560.87  6252.2 1582.84  6341.6 1606.74
#Mann= 14 ,-1 , 0
  3903.4      .1       0  3993.4    .035       0  4205.9    .045       0
  4716.3     .07       0  4854.8    .045       0  4861.7     .07       0
  5004.4    .045       0  5004.8     .05       0    5012    .045       0
  5087.4     .07       0    5323    .045       0  5431.2    .035       0
  6016.4     .07       0  6184.8    .035       0
Bank Sta=5004.8,5012
XS Rating Curve= 0 ,0
Exp/Cntr=0.3,0.1

Type RM Length L Ch R = 1 ,7282    ,443,443,443
BEGIN DESCRIPTION:
Stream0056 3.0
END DESCRIPTION:
XS GIS Cut Line= 3
      1976210.57     13914184.29        1976625.       13913925.
       1977224.1     13912511.59
#Sta/Elev= 30
  4506.9 1541.43  4623.5 1538.86  4640.1 1538.76  4716.3 1538.19  4848.8 1536.16
  4978.6 1531.36  4979.1 1530.86  4985.8 1531.36  5028.3 1536.06  5111.7 1533.49
  5420.1 1536.37  5503.9 1536.62  5878.5 1537.64  6086.1 1540.13  6168.8 1542.32
  6201.4 1545.54    6239 1542.88  6277.4 1545.36    6310 1542.05  6331.7 1547.29
  6339.1 1552.08  6368.2 1558.92  6391.9 1568.11    6421 1572.89  6439.2 1580.76
  6444.6 1580.46  6468.3 1588.75  6473.7 1587.87  6487.1 1593.84  6530.9 1608.13
#Mann= 12 ,-1 , 0
  4506.9    .035       0  4623.5     .07       0  4640.1    .035       0
  4716.3    .045       0  4848.8     .07       0  4978.6     .05       0
  4985.8     .07       0  5111.7    .045       0  5420.1     .07       0
  5503.9    .045       0  5878.5    .035       0  6487.1      .1       0
#XS Ineff= 2 , 0
                         5551.45         1540.96
Permanent Ineff=
       F       F
Bank Sta=4978.6,4985.8
XS Rating Curve= 0 ,0
Exp/Cntr=0.3,0.1

Type RM Length L Ch R = 1 ,6839    ,431,431,431
BEGIN DESCRIPTION:
Stream0056 2.0
END DESCRIPTION:
XS GIS Cut Line= 4
      1976763.94     13914490.31        1977025.       13913975.
      1977039.48     13913882.45      1977379.48     13912629.71
#Sta/Elev= 30
  4417.6 1537.45  4513.2 1537.83  4766.5 1532.48    4776  1532.2  4892.2 1530.97
  4986.9 1528.72  5005.4 1527.31  5015.5 1525.12  5025.5 1520.17    5026 1519.67
  5032.8 1520.17  5045.9 1528.13    5056 1529.68  5085.1 1531.69  5280.1 1533.11
  5788.2 1534.11  5956.7 1536.01  6091.4 1536.56  6124.7 1537.17  6153.6  1539.9
  6164.5 1538.38    6238 1538.31  6243.1 1538.59  6273.6 1539.94  6319.3  1539.2
  6340.1 1541.05    6348 1543.79  6353.2 1544.26  6381.5    1554    6387 1558.05
#Mann= 9 ,-1 , 0
  4417.6     .07       0  4766.5    .045       0    4776     .07       0
  5025.5     .05       0  5032.8     .07       0  5280.1    .045       0
  5788.2    .035       0    6238    .045       0  6243.1    .035       0
#XS Ineff= 2 , 0
                         5633.37         1535.55
Permanent Ineff=
       F       F
Bank Sta=5025.5,5032.8
XS Rating Curve= 0 ,0
Exp/Cntr=0.3,0.1

Type RM Length L Ch R = 1 ,6408    ,243,243,243
BEGIN DESCRIPTION:
Stream0056 1.0
END DESCRIPTION:
XS GIS Cut Line= 3
      1977452.82      13914554.3        1977425.       13913975.
      1977462.11     13912590.77
#Sta/Elev= 30
  4424.5  1535.4  4493.9 1538.24    4584 1537.99  4744.2 1534.29  4844.3 1528.87
  4884.3 1524.86    4918 1524.97  4954.4 1524.54  4964.4  1523.5  4980.7 1518.71
  4981.2 1518.21  4988.1 1518.71  5014.5 1525.88  5272.9 1529.94  5336.5 1529.98
  5407.7 1530.02  5576.9 1530.56    5740 1531.41  6044.8 1534.11  6084.9 1537.01
  6104.9  1535.3  6125.9 1536.11  6207.7 1537.92  6284.9 1541.03  6304.9 1548.97
  6310.2 1552.96  6331.7 1562.27    6355 1575.22    6365 1578.68  6389.2 1582.72
#Mann= 12 ,-1 , 0
  4424.5    .035       0    4918     .07       0  4980.7     .05       0
  4988.1     .07       0  5272.9    .035       0  5336.5    .045       0
  5407.7    .035       0  5576.9    .045       0    5740    .035       0
  6125.9    .045       0  6207.7    .035       0  6331.7      .1       0
#XS Ineff= 2 , 0
                         5051.45         1527.41
Permanent Ineff=
       F       F
Bank Sta=4980.7,4988.1
XS Rating Curve= 0 ,0
Exp/Cntr=0.3,0.1

Type RM Length L Ch R = 1 ,6165    ,258,258,258
BEGIN DESCRIPTION:
Mapping XS 5c3d0fd6
END DESCRIPTION:
XS GIS Cut Line= 2
      1977713.56     13914412.45      1977496.63     13912621.24
#Sta/Elev= 30
  4527.6  1538.3  4635.6 1534.44  4716.4 1532.59  4736.6 1533.17  4789.8 1530.76
    4928 1527.47  4973.2 1522.81  4984.7 1517.04  4985.2 1516.54  4992.1 1517.04
  5008.5 1521.92  5038.8 1523.08  5079.1 1528.46  5112.9 1527.37  5401.3 1528.34
  5615.6 1529.65  5975.9 1532.55  6025.9 1535.02    6036 1534.04  6080.1 1534.96
  6178.5 1537.02  6221.5  1538.1  6237.5 1541.56  6247.5 1542.13  6295.9 1566.35
  6303.4 1572.12  6308.5 1569.65    6318 1574.96  6327.5 1578.68  6331.9 1578.68
#Mann= 10 ,-1 , 0
  4527.6    .035       0  4789.8     .07       0  4984.7     .05       0
  4992.1     .07       0  5112.9    .035       0  5401.3    .045       0
  5615.6    .035       0  6080.1    .045       0  6178.5    .035       0
  6295.9      .1       0
#XS Ineff= 2 , 0
                         5081.42          1528.3
Permanent Ineff=
       F       F
Bank Sta=4984.7,4992.1
XS Rating Curve= 0 ,0
Exp/Cntr=0.3,0.1