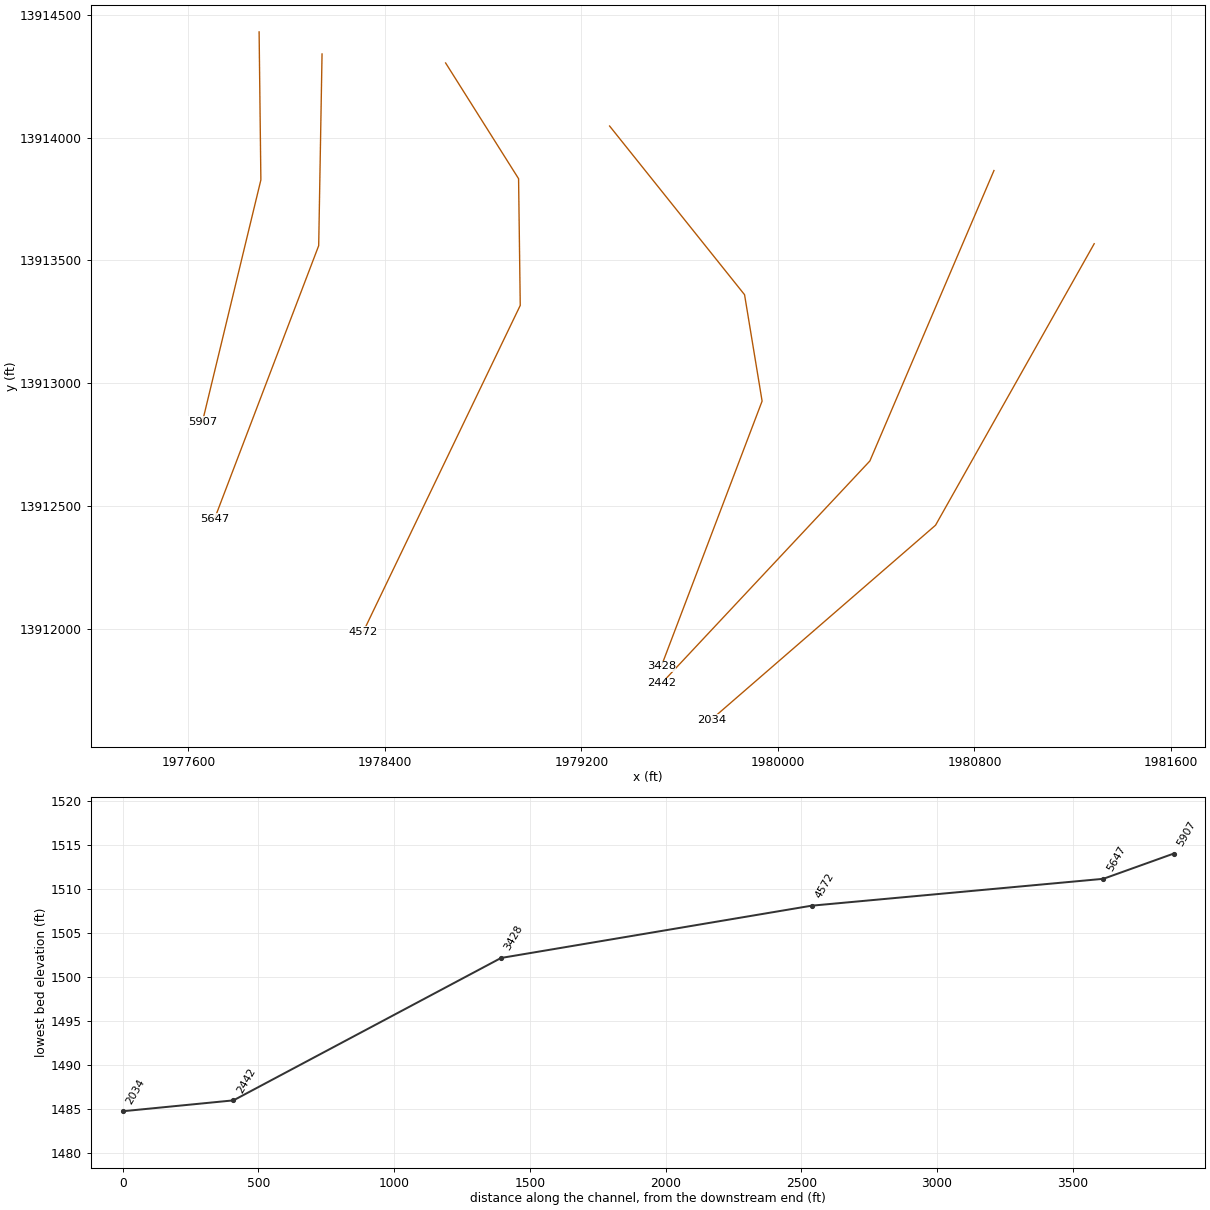
HEC-RAS study Stream0056.prj: Stream0056 Base Level Engineering

--- Stream0056.g01 (geometry) --- (continued)

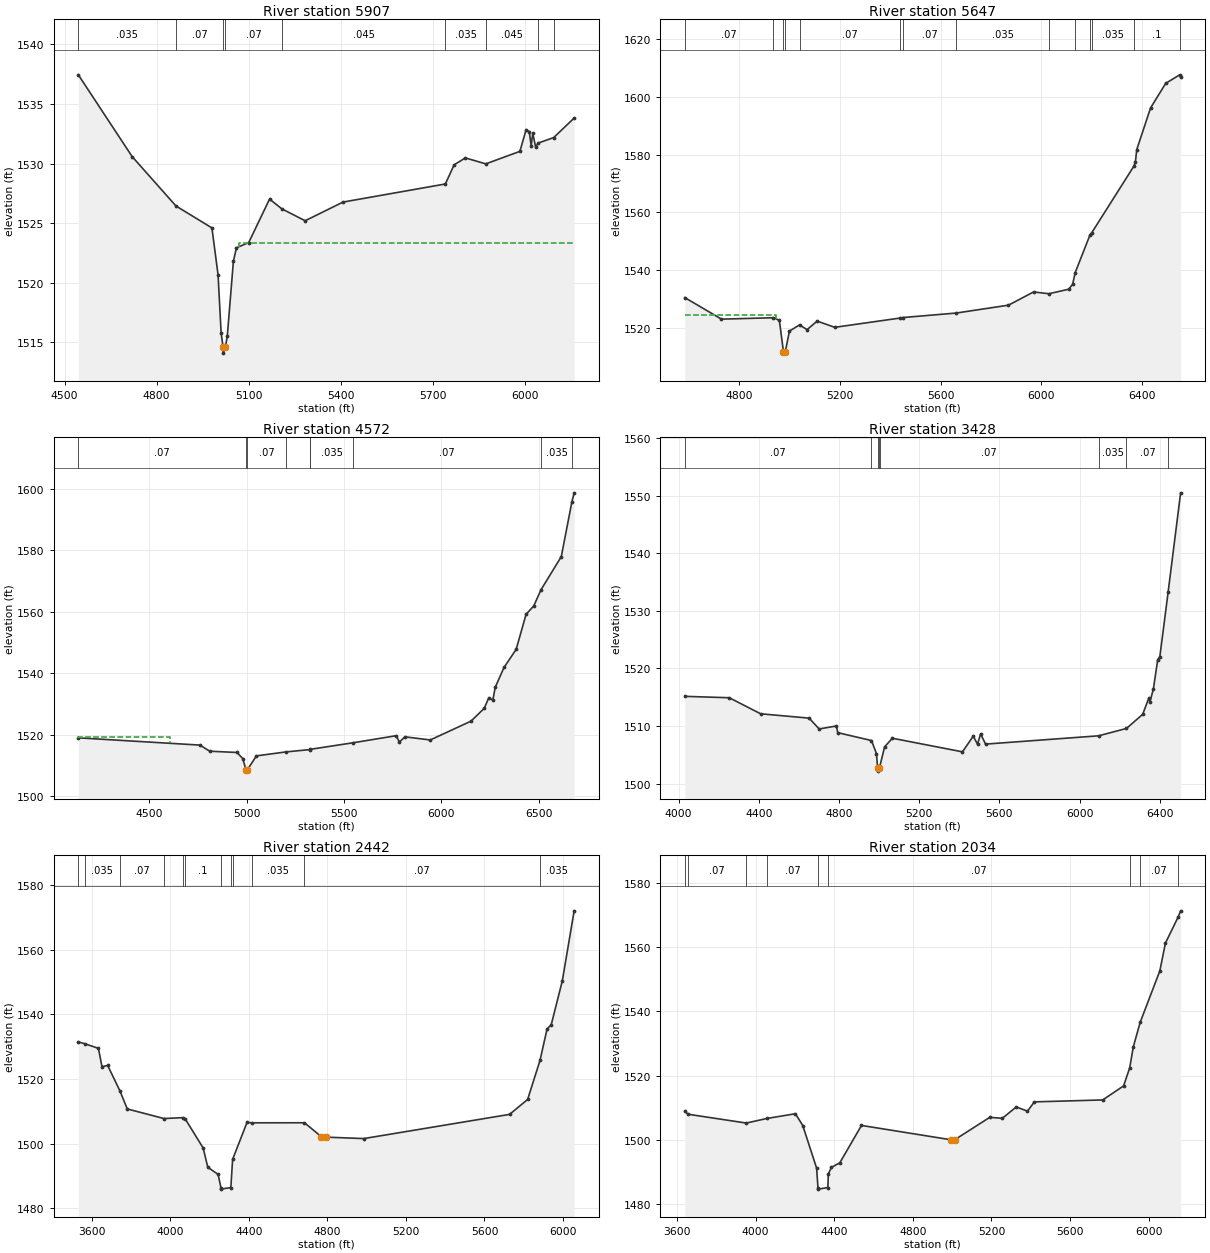
Type RM Length L Ch R = 1 ,5907    ,260,260,260
BEGIN DESCRIPTION:
Stream0056 0.0
END DESCRIPTION:
XS GIS Cut Line= 3
      1977888.22     13914430.38       1977895.4      13913827.9
      1977657.32     13912842.79
#Sta/Elev= 30
    4545 1537.45  4720.4 1530.58  4863.3 1526.43  4980.4 1524.59  5000.4 1520.65
  5010.4 1515.77  5016.7 1514.57  5017.2 1514.07  5024.1 1514.57  5030.4 1515.47
  5050.4 1521.79  5060.4 1522.92  5100.4 1523.36  5168.2 1527.01  5208.4 1526.19
  5284.2 1525.19  5407.7 1526.76  5741.3 1528.28  5769.7 1529.89  5806.4 1530.47
    5873 1529.97  5984.1 1531.02  6004.4 1532.84  6014.7 1532.67  6020.9 1531.49
    6026 1532.54  6035.3  1531.4  6044.1 1531.72  6094.4 1532.18    6161 1533.82
#Mann= 9 ,-1 , 0
    4545    .035       0  4863.3     .07       0  5016.7     .05       0
  5024.1     .07       0  5208.4    .045       0  5741.3    .035       0
    5873    .045       0  6044.1    .035       0  6094.4    .045       0
#XS Ineff= 2 , 0
                         5067.13         1523.35
Permanent Ineff=
       F       F
Bank Sta=5016.7,5024.1
XS Rating Curve= 0 ,0
Exp/Cntr=0.3,0.1

Type RM Length L Ch R = 1 ,5647    ,1075,1075,1075
BEGIN DESCRIPTION:
Stream0056 0.1
END DESCRIPTION:
XS GIS Cut Line= 3
      1978144.38     13914340.58      1978130.73     13913560.27
      1977707.14     13912449.32
#Sta/Elev= 30
  4584.3 1530.43  4729.9 1522.97  4936.5 1523.45  4959.9 1522.57  4976.2 1511.69
  4976.7 1511.19  4983.6 1511.69  4999.9 1518.82  5039.9 1520.97    5070 1519.34
    5110 1522.29    5180 1520.13  5440.4 1523.36  5449.5 1523.51  5662.6 1525.08
    5870 1527.81  5969.7 1532.39  6030.5 1531.77  6108.8 1533.32  6124.8 1535.06
  6134.8 1539.05  6193.9 1552.19  6200.6 1552.89  6367.6 1575.91  6374.1 1577.47
  6379.5 1581.72  6434.3 1596.15  6494.5 1604.67    6550 1607.62  6553.7 1606.97
#Mann= 14 ,-1 , 0
  4584.3     .07       0  4936.5      .1       0  4976.2     .05       0
  4983.6      .1       0  5039.9     .07       0  5440.4    .035       0
  5449.5     .07       0  5662.6    .035       0  6030.5    .045       0
  6134.8    .035       0  6193.9     .07       0  6200.6    .035       0
  6367.6      .1       0    6550    .035       0
#XS Ineff= 2 , 0
         4946.48 1524.43
Permanent Ineff=
       F       F
Bank Sta=4976.2,4983.6
XS Rating Curve= 0 ,0
Exp/Cntr=0.3,0.1

Type RM Length L Ch R = 1 ,4572    ,1144,1144,1144
BEGIN DESCRIPTION:
Stream0056 0.2
END DESCRIPTION:
XS GIS Cut Line= 4
      1978647.38      13914303.9      1978944.34     13913832.86
      1978951.12     13913317.08      1978312.12     13911988.86
#Sta/Elev= 30
  4135.7 1518.96  4760.4  1516.6  4810.4 1514.61  4950.4  1514.2  4980.4  1512.2
  4996.4 1508.63  4996.9 1508.13  5004.5 1508.63  5050.4 1513.09  5201.8 1514.38
  5324.3 1515.13  5326.5 1515.22  5547.4 1517.36  5767.8 1519.65  5784.9  1517.6
  5813.1 1519.29  5943.1 1518.27  6152.5 1524.39  6220.4 1528.56  6242.7 1531.83
  6264.9 1531.32  6276.8 1535.37    6322 1541.85  6384.4 1547.74  6435.2 1559.12
  6474.9 1561.89  6512.4 1567.18  6616.2 1577.92    6671 1595.84  6682.3 1598.67
#Mann= 9 ,-1 , 0
  4135.7     .07       0  4996.4     .05       0  5004.5     .07       0
  5201.8    .035       0  5324.3     .07       0  5326.5    .035       0
  5547.4     .07       0  6512.4    .035       0    6671     .07       0
#XS Ineff= 2 , 0
         4608.39 1519.16
Permanent Ineff=
       F       F
Bank Sta=4996.4,5004.5
XS Rating Curve= 0 ,0
Exp/Cntr=0.3,0.1

Type RM Length L Ch R = 1 ,3428    ,986,986,986
BEGIN DESCRIPTION:
Stream0056 0.3
END DESCRIPTION:
XS GIS Cut Line= 4
      1979314.75     13914047.27      1979864.14     13913360.68
      1979935.54     13912927.57      1979525.22     13911848.13
#Sta/Elev= 30
  4030.8 1515.16  4252.6 1514.92  4409.4 1512.13  4651.1 1511.38  4700.8  1509.5
  4787.2 1510.02  4793.6 1508.86  4961.9 1507.49  4986.8 1505.23  4992.9 1502.68
  4993.4 1502.18  5001.1 1502.68  5002.4 1502.83  5027.4 1506.39    5066 1507.89
  5415.8 1505.53  5469.5 1508.25  5490.9 1506.85  5506.2 1508.65    5531 1506.87
  6094.6 1508.31  6233.8 1509.59  6314.7 1512.04  6345.6 1514.88  6350.9 1514.18
  6368.2 1516.47  6389.6 1521.51  6400.3 1522.06  6441.8 1533.32  6503.9 1550.49
#Mann= 8 ,-1 , 0
  4030.8     .07       0  4961.9      .1       0  4992.9     .05       0
  5001.1      .1       0  5002.4     .07       0  6094.6    .035       0
  6233.8     .07       0  6441.8    .035       0
Bank Sta=4992.9,5001.1
XS Rating Curve= 0 ,0
Exp/Cntr=0.3,0.1

Type RM Length L Ch R = 1 ,2442    ,408,408,408
BEGIN DESCRIPTION:
Stream0056 0.9
END DESCRIPTION:
XS GIS Cut Line= 3
      1980879.31     13913866.11      1980374.09      13912683.8
       1979526.3      13911778.8
#Sta/Elev= 30
    3531 1531.46  3563.6  1530.9  3633.3 1529.48  3651.4 1523.82  3680.5 1524.18
  3742.4 1516.39  3780.3 1510.75  3967.4 1507.78  4062.9 1508.06  4075.8 1507.64
  4166.9 1498.68  4190.5 1492.73  4243.2 1490.51  4257.3 1486.47  4258.3 1485.97
  4307.9 1486.47    4317 1495.18  4390.2 1506.56  4413.5 1506.46  4683.1 1506.48
 4769.33 1502.15 4790.53 1502.04    4985 1501.59  5727.9 1509.07  5819.8 1513.68
  5882.8 1525.74  5918.9  1535.5    5940 1536.76  5996.6 1550.37  6056.8 1571.97
#Mann= 12 ,-1 , 0
    3531     .07       0  3563.6    .035       0  3742.4     .07       0
  3967.4    .035       0  4062.9     .07       0  4075.8      .1       0
  4257.3     .05       0  4307.9      .1       0    4317     .07       0
  4413.5    .035       0  4683.1     .07       0  5882.8    .035       0
#Block Obstruct= 2 , 0
         4378.12 1500.96
Bank Sta=4769.33,4790.53
XS Rating Curve= 0 ,0
Exp/Cntr=0.3,0.1

Type RM Length L Ch R = 1 ,2034    ,0,0,0
BEGIN DESCRIPTION:
Stream0056 0.5
END DESCRIPTION:
XS GIS Cut Line= 3
      1981287.28     13913568.16      1980641.45     13912422.35
      1979729.14     13911631.44
#Sta/Elev= 30
  3639.7 1509.03  3655.5 1508.03  3952.7 1505.28  4056.8  1506.7  4202.2 1508.18
  4239.8 1504.52  4310.5 1491.23  4317.1 1485.23  4318.1 1484.73  4367.7 1485.23
  4369.8 1489.43  4385.7 1491.48  4428.4 1492.92  4538.7 1504.54 4996.14 1500.06
 5012.29 1500.06  5191.3 1507.06    5255 1506.75  5326.2 1510.29  5383.2 1508.98
  5418.3 1511.87    5766 1512.47  5872.3 1516.84  5903.4 1522.47  5921.7 1528.99
  5956.6 1536.61  6056.6  1552.6  6085.1 1561.25  6149.5 1569.32  6162.4 1571.29
#Mann= 9 ,-1 , 0
  3639.7      .1       0  3655.5     .07       0  3952.7    .035       0
  4056.8     .07       0  4317.1     .05       0  4367.7     .07       0
  5903.4    .035       0  5956.6     .07       0  6149.5    .035       0
#Block Obstruct= 2 , 0
            4501 1499.56
Bank Sta=4996.14,5012.29
XS Rating Curve= 0 ,0
Exp/Cntr=0.3,0.1

Chan Stop Cuts=-1
Use User Specified Reach Order=0
Composite Channel Slope=5