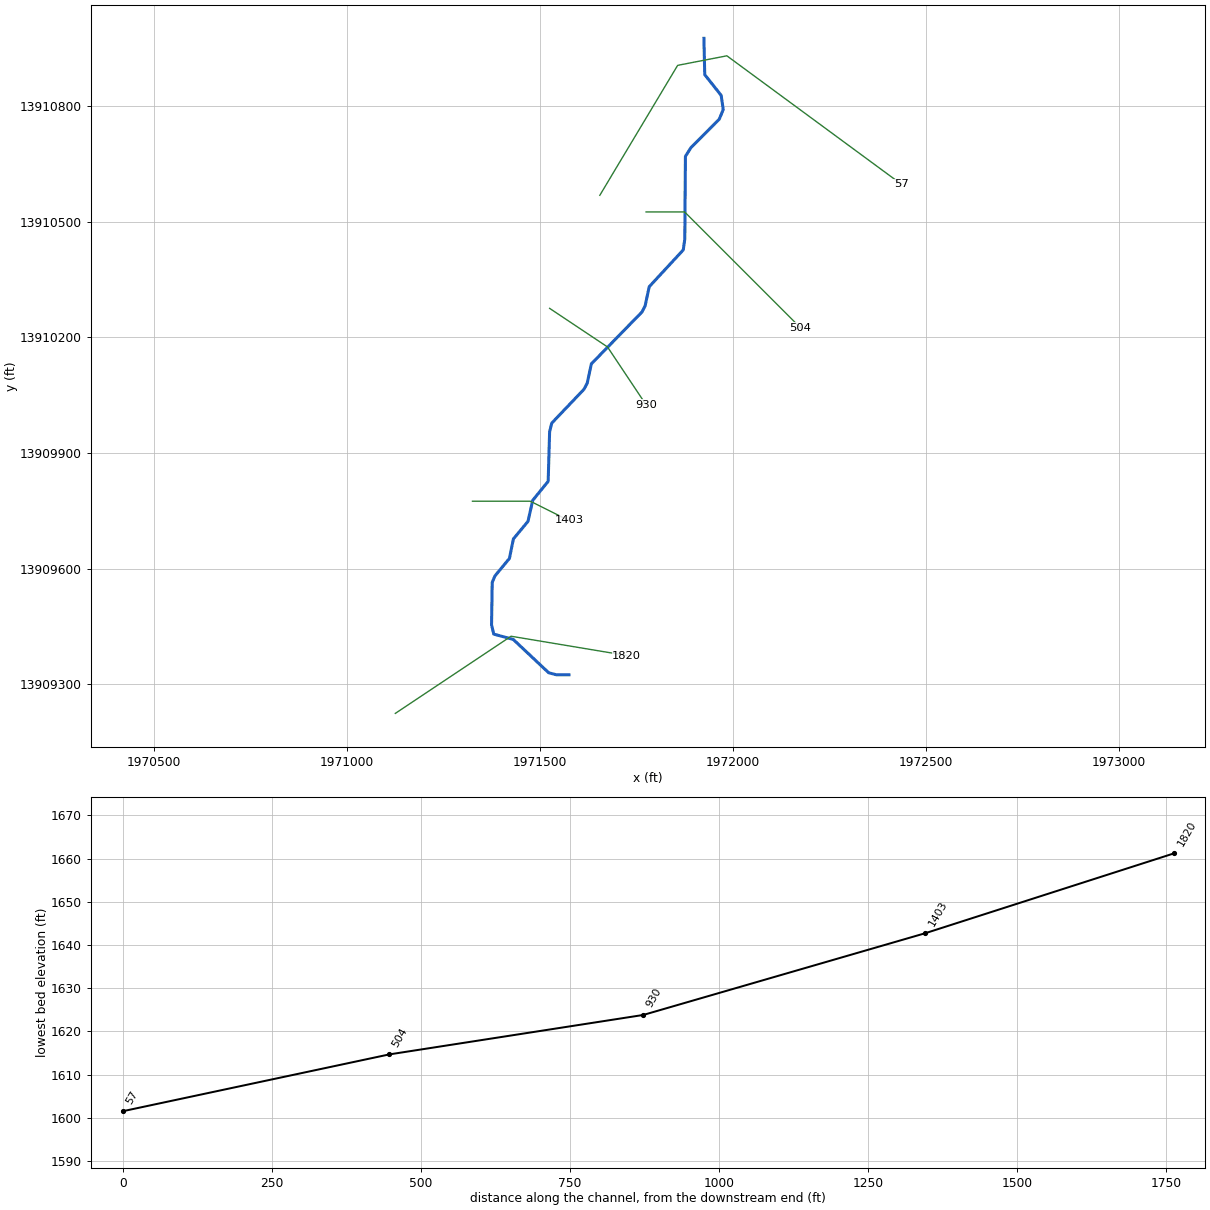
--- Stream0057.prj (project) ---

Proj Title=Stream0057 Base Level Engineering
Current Plan=p01
Default Exp/Contr=0.3,0.1
English Units
Geom File=g01
Flow File=f01
Plan File=p01
BEGIN DESCRIPTION:
Stream0057
END DESCRIPTION:

--- Stream0057.p01 (plan) ---

Plan Title=Multiple Run
Short Identifier=Multiple
Geom File=g01
Flow File=f01
Subcritical Flow
K Sum by GR= 0
Std Step Tol= 0.01
Critical Tol= 0.01
Num of Std Step Trials= 20
Max Error Tol= 0.3
Flow Tol Ratio= 0.001
Split Flow NTrial= 30
Split Flow Tol= 0.02
Split Flow Ratio= 0.02
Log Output Level= 0
Friction Slope Method= 1
Unsteady Friction Slope Method= 2
Unsteady Bridges Friction Slope Method= 1
Parabolic Critical Depth
Global Vel Dist=  1 , 1 , 1
Global Log Level= 0
CheckData=True
Encroach Param= -1, 0, 0, 0
BEGIN DESCRIPTION:
Multiple Run
END DESCRIPTION:

--- Stream0057.f01 (steady flow) ---

Flow Title=Multiple
Number of Profiles=7
Profile Names=10-year,25-year,50-year,1pct_min,100-year,1pct_plu,500-year
River Rch & RM= Stream0057,Reach-1,1820
     315     502     669     436     870    1736    1447
Boundary for River Rch & Prof#=Stream0057,Reach-1,1
Up Type=0
Dn Type=3
Dn Slope=0.005
Boundary for River Rch & Prof#=Stream0057,Reach-1,2
Up Type=0
Dn Type=3
Dn Slope=0.005
Boundary for River Rch & Prof#=Stream0057,Reach-1,3
Up Type=0
Dn Type=3
Dn Slope=0.005
Boundary for River Rch & Prof#=Stream0057,Reach-1,4
Up Type=0
Dn Type=3
Dn Slope=0.005
Boundary for River Rch & Prof#=Stream0057,Reach-1,5
Up Type=0
Dn Type=3
Dn Slope=0.005
Boundary for River Rch & Prof#=Stream0057,Reach-1,6
Up Type=0
Dn Type=3
Dn Slope=0.005
Boundary for River Rch & Prof#=Stream0057,Reach-1,7
Up Type=0
Dn Type=3
Dn Slope=0.005

--- Stream0057.g01 (geometry) ---

Geom Title=Existing Conditions

River Reach=Stream0057,Reach-1
Reach XY= 30
      1971575.00     13909325.00      1971543.12     13909324.93
      1971522.49     13909330.33      1971430.69     13909416.69
      1971380.17     13909430.44      1971374.43     13909454.58
      1971376.18     13909564.49      1971383.09     13909581.07
      1971420.81     13909626.74      1971431.08     13909677.20
      1971468.92     13909722.80      1971481.12     13909777.18
      1971521.24     13909826.56      1971524.98     13909955.01
      1971530.48     13909977.44      1971614.20     13910065.33
      1971622.46     13910081.05      1971633.16     13910131.05
      1971764.22     13910265.32      1971772.47     13910281.05
      1971783.18     13910331.04      1971871.45     13910426.47
      1971875.43     13910454.82      1971877.07     13910669.14
      1971891.47     13910691.75      1971964.79     13910765.33
      1971975.05     13910790.34      1971969.70     13910827.18
      1971927.13     13910880.86      1971925.00     13910975.00

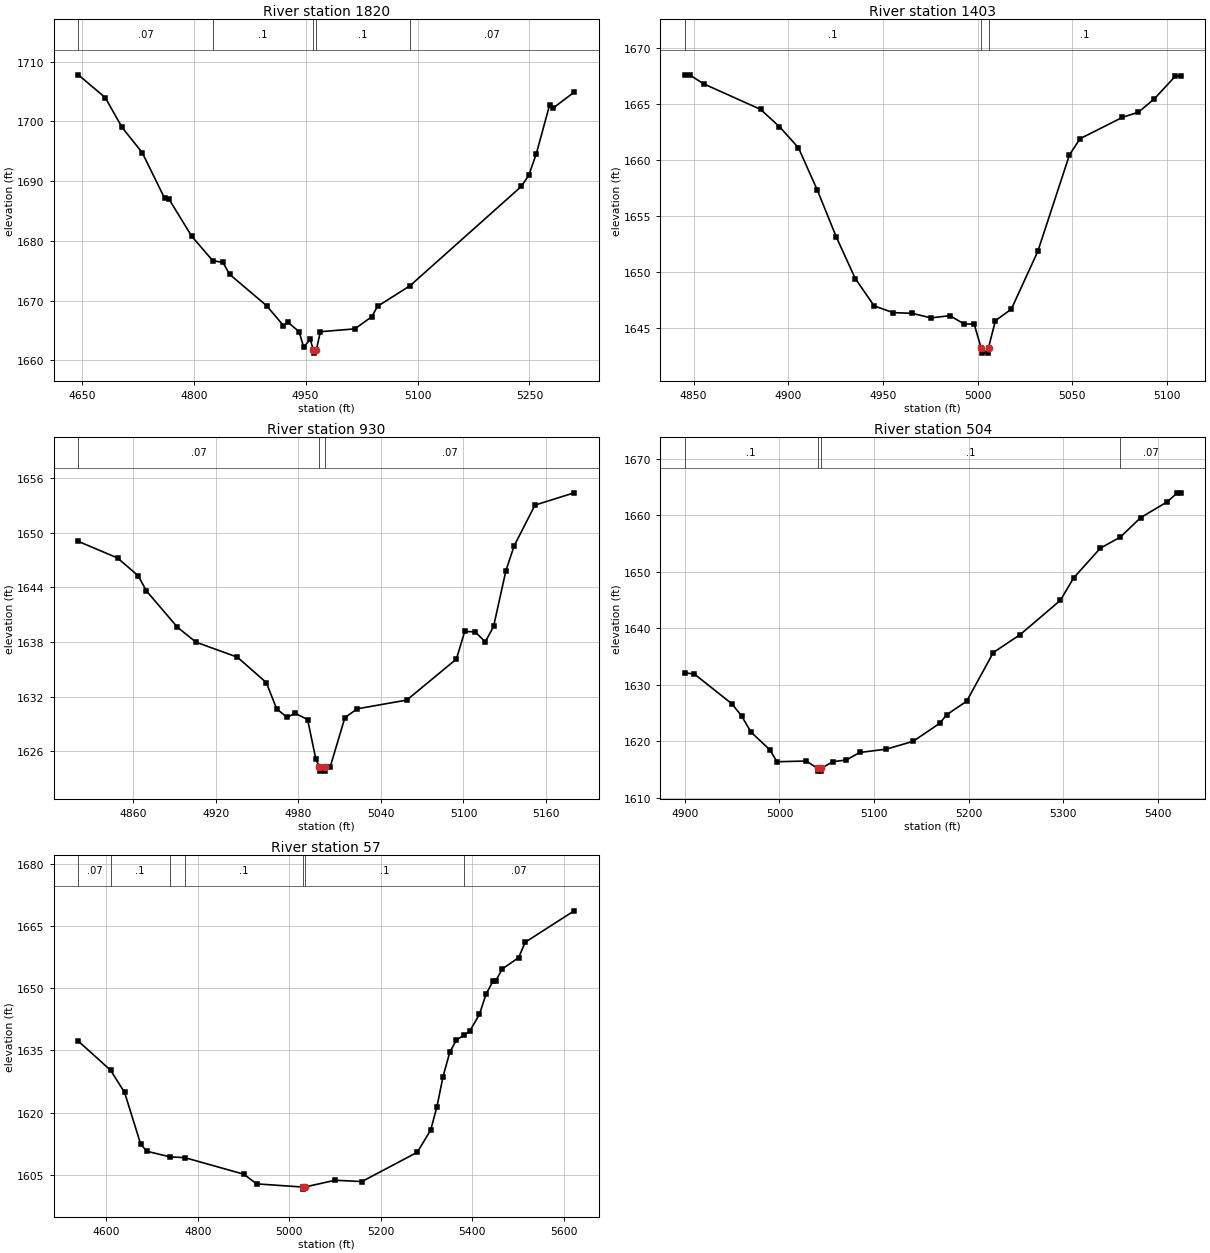
Type RM Length L Ch R = 1,1820,417,417,417
BEGIN DESCRIPTION:
Stream0057 4.0
END DESCRIPTION:
XS GIS Cut Line= 3
      1971124.98     13909224.98      1971425.00     13909425.00
      1971724.98     13909375.00
#Sta/Elev= 30
  4645.3 1707.81  4681.4 1703.99  4703.9 1699.01  4731.0 1694.77  4761.0 1687.13
  4767.0 1686.96  4797.1 1680.81  4825.4 1676.69  4839.1 1676.39  4848.1 1674.40
  4897.7 1669.14  4920.3 1665.81  4926.3 1666.36  4941.3 1664.79  4947.3 1662.22
  4956.3 1663.50  4960.3 1661.70  4960.6 1661.20  4964.3 1661.70  4969.8 1664.79
  5016.0 1665.26  5038.8 1667.31  5046.4 1669.04  5089.9 1672.48  5239.1 1689.11
  5249.2 1690.99  5259.3 1694.61  5277.1 1702.76  5282.1 1702.27  5310.0 1704.90
#Mann=5,-1,0
  4645.3    0.07       0  4825.4     0.1       0  4960.3    0.05       0
  4964.3     0.1       0  5089.9    0.07       0
Bank Sta=4960.3,4964.3
Exp/Cntr=0.3,0.1

Type RM Length L Ch R = 1,1403,473,473,473
BEGIN DESCRIPTION:
Stream0057 3.0
END DESCRIPTION:
XS GIS Cut Line= 3
      1971324.97     13909775.00      1971475.00     13909775.00
      1971574.97     13909725.01
#Sta/Elev= 30
  4845.4 1667.61  4847.9 1667.61  4855.4 1666.80  4885.4 1664.52  4895.4 1662.97
  4905.4 1661.09  4915.4 1657.29  4925.4 1653.11  4935.4 1649.40  4945.4 1646.95
  4955.4 1646.35  4965.4 1646.29  4975.4 1645.88  4985.4 1646.08  4992.9 1645.33
  4998.2 1645.33  5001.8 1643.23  5002.1 1642.73  5005.6 1642.73  5005.8 1643.23
  5009.4 1645.63  5017.8 1646.66  5031.8 1651.83  5048.5 1660.45  5054.1 1661.90
  5076.5 1663.81  5084.9 1664.27  5093.3 1665.46  5104.4 1667.49  5107.2 1667.49
#Mann=3,-1,0
  4845.4     0.1       0  5001.8    0.05       0  5005.8     0.1       0
Bank Sta=5001.8,5005.8
Exp/Cntr=0.3,0.1

Type RM Length L Ch R = 1,930,426,426,426
BEGIN DESCRIPTION:
Stream0057 2.0
END DESCRIPTION:
XS GIS Cut Line= 3
      1971525.04     13910274.97      1971675.00     13910175.00
      1971775.00     13910025.01
#Sta/Elev= 30
  4820.0 1649.06  4848.5 1647.24  4863.5 1645.29  4869.5 1643.62  4892.1 1639.62
  4905.6 1637.98  4935.6 1636.34  4956.7 1633.54  4964.2 1630.65  4971.7 1629.73
  4977.7 1630.16  4986.7 1629.48  4992.7 1625.11  4995.2 1624.31  4995.5 1623.81
  4999.0 1623.81  4999.2 1624.31  5003.2 1624.31  5013.8 1629.69  5022.8 1630.66
  5058.8 1631.62  5094.9 1636.13  5100.9 1639.16  5108.4 1639.12  5115.9 1638.02
  5121.9 1639.71  5130.9 1645.86  5136.9 1648.58  5152.0 1653.05  5180.5 1654.40
#Mann=3,-1,0
  4820.0    0.07       0  4995.2    0.05       0  4999.2    0.07       0
Bank Sta=4995.2,4999.2
Exp/Cntr=0.3,0.1

Type RM Length L Ch R = 1,504,447,447,447
BEGIN DESCRIPTION:
Stream0057 1.0
END DESCRIPTION:
XS GIS Cut Line= 3
      1971775.03     13910525.00      1971875.00     13910525.00
      1972174.97     13910225.03
#Sta/Elev= 30
  4899.9 1632.08  4909.9 1631.89  4949.9 1626.58  4959.9 1624.46  4969.9 1621.59
  4989.9 1618.44  4997.4 1616.34  5028.2 1616.47  5040.3 1615.18  5040.5 1614.68
  5044.0 1614.68  5044.3 1615.18  5056.4 1616.36  5070.6 1616.64  5084.7 1617.98
  5113.0 1618.57  5141.3 1619.96  5169.6 1623.17  5176.6 1624.65  5197.9 1627.06
  5226.1 1635.69  5254.4 1638.85  5296.9 1644.92  5311.0 1648.90  5339.3 1654.18
  5360.5 1656.14  5381.7 1659.56  5410.0 1662.38  5420.6 1663.97  5424.1 1663.97
#Mann=4,-1,0
  4899.9     0.1       0  5040.3    0.05       0  5044.3     0.1       0
  5360.5    0.07       0
Bank Sta=5040.3,5044.3
Exp/Cntr=0.3,0.1

Type RM Length L Ch R = 1,57,0,0,0
BEGIN DESCRIPTION:
Stream0057 0.0
END DESCRIPTION:
XS GIS Cut Line= 4
      1971655.16     13910568.10      1971856.91     13910904.95
      1971984.51     13910929.69      1972436.61     13910597.08
#Sta/Elev= 30
  4538.7 1637.26  4609.3 1630.22  4639.8 1624.87  4675.0 1612.38  4688.4 1610.68
  4738.6 1609.33  4771.9 1609.12  4900.4 1605.13  4928.5 1602.80  5029.3 1602.03
  5029.5 1601.53  5033.3 1602.03  5100.0 1603.67  5158.6 1603.36  5279.7 1610.43
  5309.0 1615.81  5322.6 1621.40  5336.0 1628.72  5350.7 1634.58  5365.3 1637.56
  5382.1 1638.70  5394.6 1639.71  5415.5 1643.72  5430.1 1648.64  5444.8 1651.67
  5451.0 1651.77  5465.6 1654.71  5501.1 1657.40  5515.7 1661.15  5622.6 1668.72
#Mann=7,-1,0
  4538.7    0.07       0  4609.3     0.1       0  4738.6    0.07       0
  4771.9     0.1       0  5029.3    0.05       0  5033.3     0.1       0
  5382.1    0.07       0
Bank Sta=5029.3,5033.3
Exp/Cntr=0.3,0.1

Chan Stop Cuts=-1