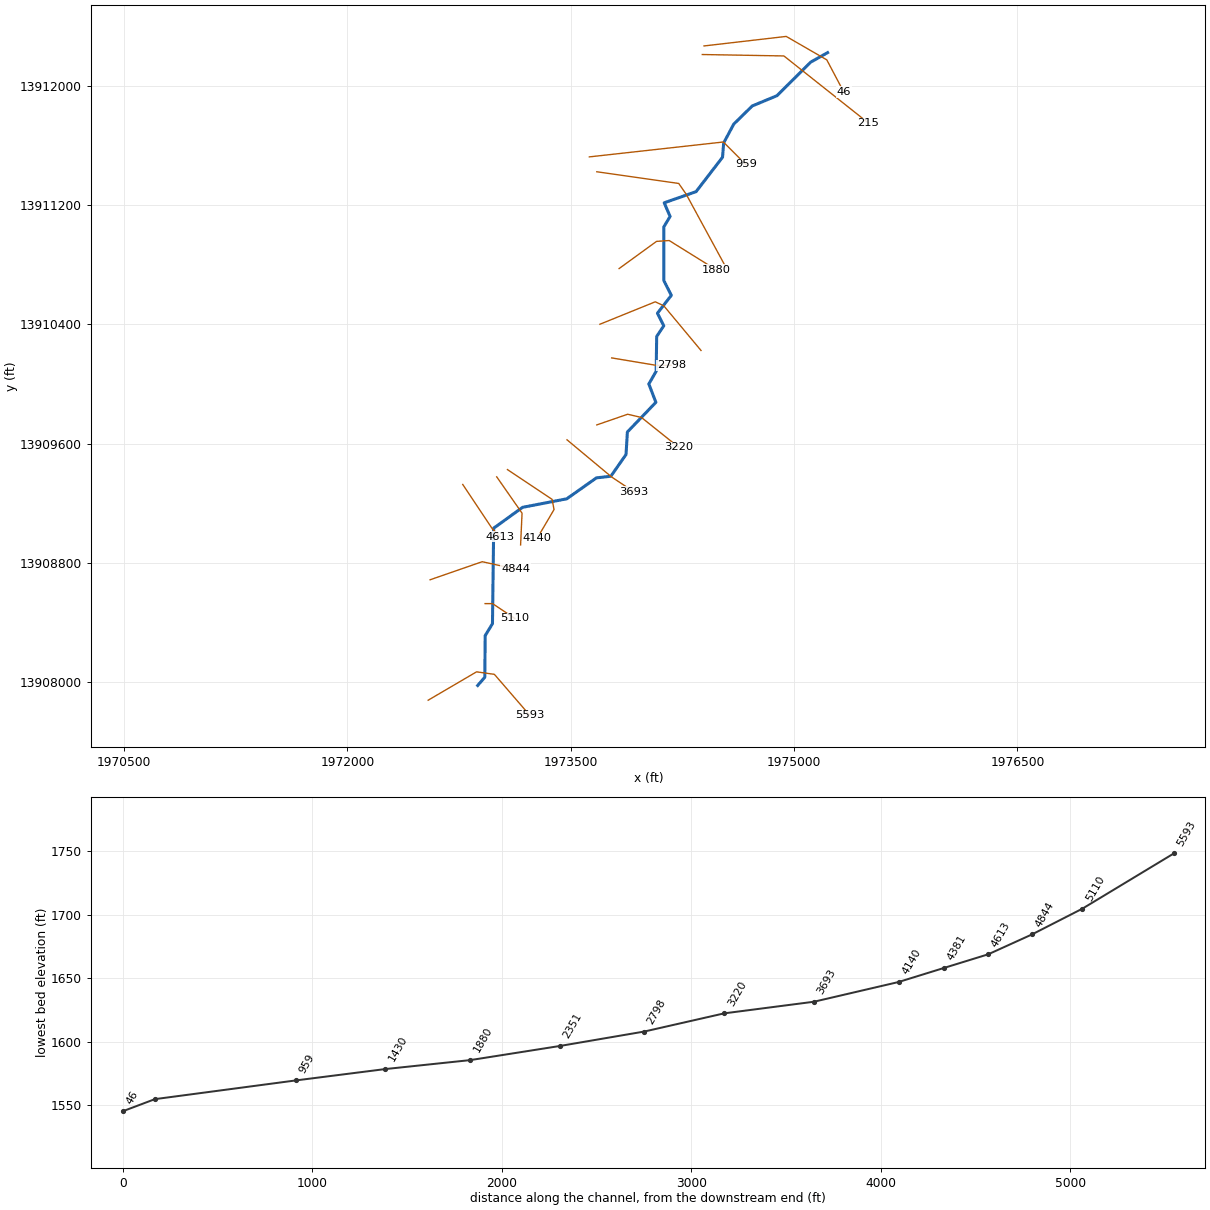
--- Stream0059.prj (project) ---

Proj Title=Stream0059 Base Level Engineering
Current Plan=p01
Default Exp/Contr=0.3,0.1
English Units
Geom File=g01
Flow File=f01
Plan File=p01
BEGIN DESCRIPTION:
Stream0059
END DESCRIPTION:

--- Stream0059.p01 (plan) ---

Plan Title=Multiple Run
Short Identifier=Multiple
Geom File=g01
Flow File=f01
Subcritical Flow
K Sum by GR= 0
Std Step Tol= 0.01
Critical Tol= 0.01
Num of Std Step Trials= 20
Max Error Tol= 0.3
Flow Tol Ratio= 0.001
Split Flow NTrial= 30
Split Flow Tol= 0.02
Split Flow Ratio= 0.02
Log Output Level= 0
Friction Slope Method= 1
Unsteady Friction Slope Method= 2
Unsteady Bridges Friction Slope Method= 1
Parabolic Critical Depth
Global Vel Dist=  1 , 1 , 1
Global Log Level= 0
CheckData=True
Encroach Param= -1, 0, 0, 0
BEGIN DESCRIPTION:
Multiple Run
END DESCRIPTION:

--- Stream0059.f01 (steady flow) ---

Flow Title=Multiple
Number of Profiles=7
Profile Names=10-year,25-year,50-year,1pct_min,100-year,1pct_plu,500-year
River Rch & RM= Stream0059,Reach-1,5593
     217     337     443     284     568    1133     917
River Rch & RM= Stream0059,Reach-1,4381
     953    1640    2306    1574    3141    6268    5768
Boundary for River Rch & Prof#=Stream0059,Reach-1,1
Up Type=0
Dn Type=3
Dn Slope=0.005
Boundary for River Rch & Prof#=Stream0059,Reach-1,2
Up Type=0
Dn Type=3
Dn Slope=0.005
Boundary for River Rch & Prof#=Stream0059,Reach-1,3
Up Type=0
Dn Type=3
Dn Slope=0.005
Boundary for River Rch & Prof#=Stream0059,Reach-1,4
Up Type=0
Dn Type=3
Dn Slope=0.005
Boundary for River Rch & Prof#=Stream0059,Reach-1,5
Up Type=0
Dn Type=3
Dn Slope=0.005
Boundary for River Rch & Prof#=Stream0059,Reach-1,6
Up Type=0
Dn Type=3
Dn Slope=0.005
Boundary for River Rch & Prof#=Stream0059,Reach-1,7
Up Type=0
Dn Type=3
Dn Slope=0.005

--- Stream0059.g01 (geometry) ---

Geom Title=Existing Conditions

River Reach=Stream0059,Reach-1
Reach XY= 30
      1972875.00     13907975.00      1972923.11     13908030.78
      1972925.52     13908309.78      1972974.48     13908390.22
      1972982.69     13909031.48      1973176.47     13909171.45
      1973473.42     13909228.83      1973672.64     13909369.44
      1973769.53     13909380.26      1973871.45     13909526.47
      1973880.47     13909677.45      1974071.87     13909876.63
      1974024.61     13910000.00      1974073.76     13910085.50
      1974077.29     13910319.07      1974124.85     13910390.42
      1974082.36     13910475.08      1974175.39     13910595.13
      1974125.09     13910695.03      1974125.18     13911055.02
      1974167.39     13911125.04      1974127.66     13911216.53
      1974341.79     13911291.44      1974519.46     13911522.58
      1974527.33     13911619.03      1974594.78     13911745.09
      1974718.94     13911866.86      1974884.68     13911935.76
      1975111.77     13912161.43      1975225.00     13912225.00

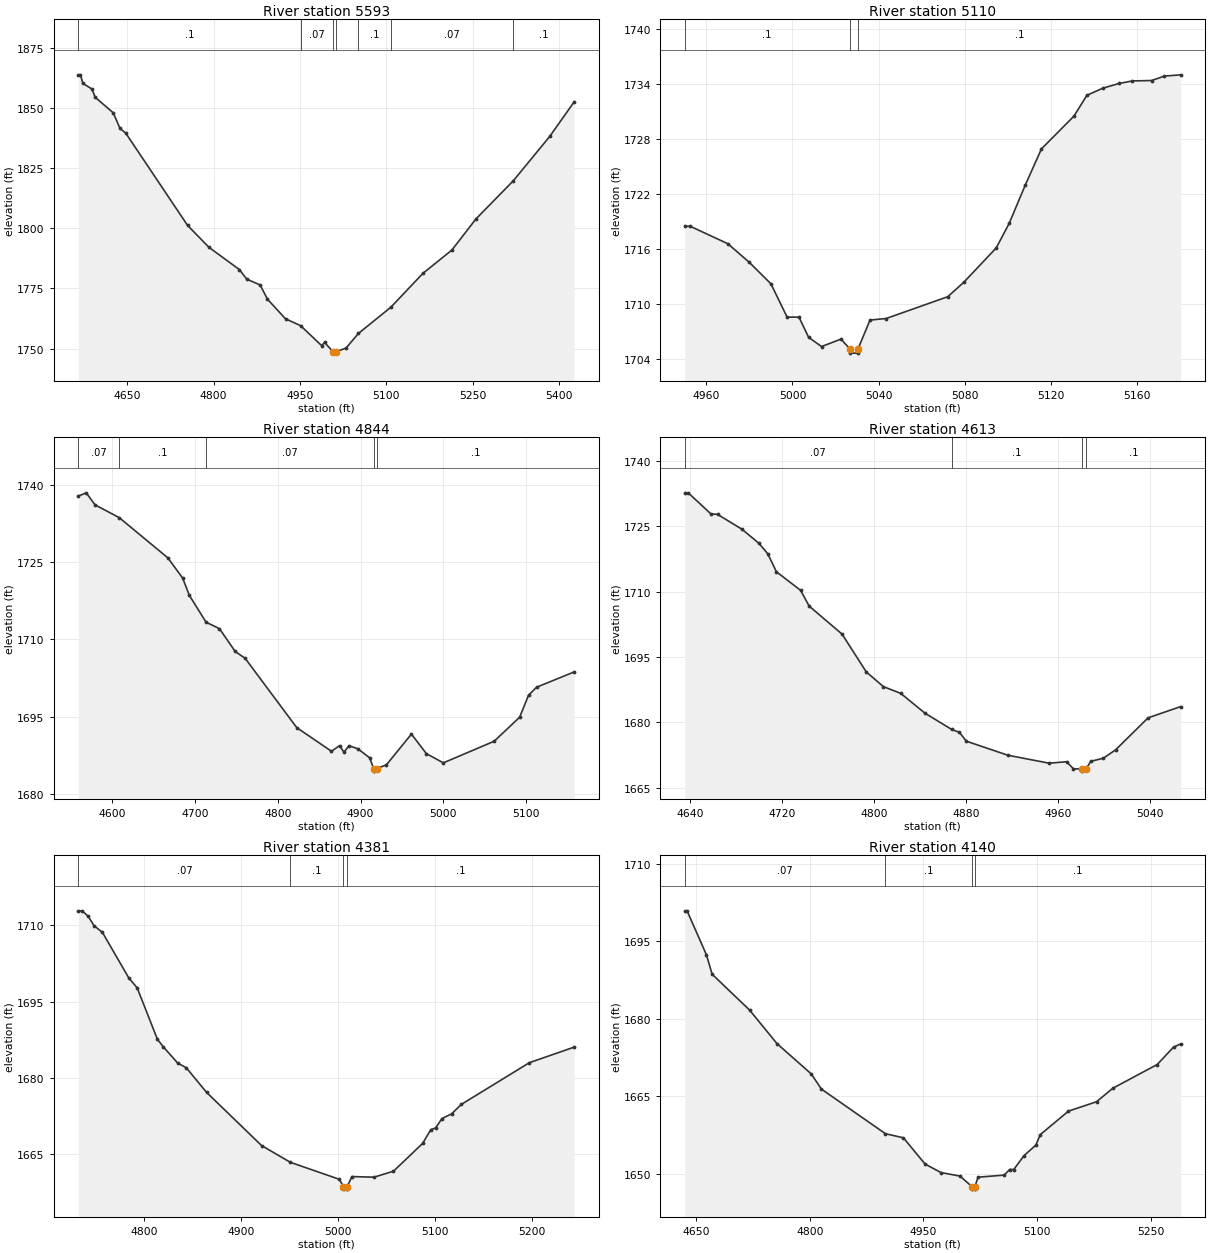
Type RM Length L Ch R = 1,5593,483,483,483
BEGIN DESCRIPTION:
Stream0059 11.0
END DESCRIPTION:
XS GIS Cut Line= 4
      1972542.67     13907876.27      1972867.70     13908066.79
      1972987.41     13908050.02      1973225.03     13907774.97
#Sta/Elev= 30
  4565.0 1863.77  4568.7 1863.77  4572.9 1860.19  4588.6 1857.89  4594.4 1854.41
  4625.7 1847.97  4637.4 1841.47  4647.3 1839.56  4754.7 1801.19  4791.8 1792.09
  4844.7 1782.82  4857.5 1778.85  4880.7 1776.45  4893.4 1770.54  4924.8 1762.37
  4951.1 1759.50  4987.6 1751.21  4992.6 1752.53  5007.7 1748.60  5008.0 1748.10
  5011.7 1748.60  5029.9 1750.20  5051.4 1756.28  5107.9 1767.21  5163.4 1781.24
  5213.8 1790.95  5255.5 1803.86  5320.6 1819.78  5383.8 1838.20  5426.1 1852.55
#Mann=7,-1,0
  4565.0     0.1       0  4951.1    0.07       0  5007.7    0.05       0
  5011.7    0.07       0  5051.4     0.1       0  5107.9    0.07       0
  5320.6     0.1       0
Bank Sta=5007.7,5011.7
Exp/Cntr=0.3,0.1

Type RM Length L Ch R = 1,5110,266,266,266
BEGIN DESCRIPTION:
Stream0059 10.0
END DESCRIPTION:
XS GIS Cut Line= 3
      1972925.03     13908525.00      1972975.00     13908525.00
      1973124.96     13908425.02
#Sta/Elev= 30
  4950.0 1718.50  4952.5 1718.50  4970.0 1716.59  4980.0 1714.55  4990.0 1712.21
  4997.5 1708.58  5003.0 1708.58  5007.5 1706.37  5013.5 1705.37  5022.5 1706.18
  5026.5 1705.15  5026.8 1704.65  5030.3 1704.65  5030.5 1705.15  5036.0 1708.26
  5043.5 1708.43  5072.1 1710.81  5079.6 1712.40  5094.6 1716.14  5100.6 1718.81
  5108.1 1723.01  5115.6 1726.95  5130.7 1730.53  5136.7 1732.80  5144.2 1733.58
  5151.7 1734.09  5157.7 1734.36  5166.7 1734.41  5172.7 1734.89  5180.2 1735.03
#Mann=3,-1,0
  4950.0     0.1       0  5026.5    0.05       0  5030.5     0.1       0
Bank Sta=5026.5,5030.5
Exp/Cntr=0.3,0.1

Type RM Length L Ch R = 1,4844,231,231,231
BEGIN DESCRIPTION:
Mapping XS eb7ba89a
END DESCRIPTION:
XS GIS Cut Line= 3
      1972555.89     13908685.10      1972905.54     13908806.39
      1973129.41     13908757.18
#Sta/Elev= 30
  4558.8 1737.89  4568.4 1738.52  4579.0 1736.18  4608.3 1733.69  4667.1 1725.86
  4684.9 1721.94  4693.0 1718.57  4713.2 1713.36  4729.4 1712.10  4748.4 1707.67
  4760.5 1706.32  4822.8 1692.86  4864.8 1688.26  4874.5 1689.36  4879.8 1688.09
  4886.0 1689.34  4896.6 1688.75  4910.9 1686.99  4915.7 1684.90  4916.0 1684.40
  4919.7 1684.90  4931.2 1685.63  4961.4 1691.60  4979.5 1687.80  5000.0 1686.01
  5061.4 1690.21  5092.2 1694.88  5103.0 1699.17  5112.6 1700.71  5158.1 1703.69
#Mann=5,-1,0
  4558.8    0.07       0  4608.3     0.1       0  4713.2    0.07       0
  4915.7    0.05       0  4919.7     0.1       0
Bank Sta=4915.7,4919.7
Exp/Cntr=0.3,0.1

Type RM Length L Ch R = 1,4613,232,232,232
BEGIN DESCRIPTION:
Stream0059 9.0
END DESCRIPTION:
XS GIS Cut Line= 3
      1972774.98     13909325.04      1972975.00     13909025.00
      1973024.99     13908975.01
#Sta/Elev= 30
  4635.3 1732.70  4638.3 1732.70  4657.9 1727.89  4663.9 1727.73  4684.9 1724.36
  4699.9 1721.08  4707.5 1718.69  4715.0 1714.57  4736.0 1710.31  4743.5 1706.68
  4772.1 1700.25  4793.1 1691.59  4808.1 1688.18  4823.1 1686.65  4844.2 1682.09
  4867.3 1678.38  4874.2 1677.68  4880.2 1675.66  4916.3 1672.43  4952.3 1670.60
  4967.4 1670.94  4973.4 1669.31  4980.4 1669.28  4980.6 1668.78  4984.4 1669.28
  4988.4 1671.03  4999.4 1671.75  5010.0 1673.66  5038.3 1681.02  5066.6 1683.60
#Mann=4,-1,0
  4635.3    0.07       0  4867.3     0.1       0  4980.4    0.05       0
  4984.4     0.1       0
Bank Sta=4980.4,4984.4
Exp/Cntr=0.3,0.1

Type RM Length L Ch R = 1,4381,241,241,241
BEGIN DESCRIPTION:
Mapping XS e91072c0
END DESCRIPTION:
XS GIS Cut Line= 3
      1973002.94     13909376.44      1973173.16     13909132.32
      1973163.40     13908918.85
#Sta/Elev= 30
  4732.0 1712.86  4735.9 1712.86  4742.1 1711.80  4748.2 1709.94  4756.9 1708.60
  4784.0 1699.67  4792.7 1697.70  4813.6 1687.57  4819.7 1686.09  4834.6 1682.89
  4843.3 1682.00  4864.2 1677.16  4920.9 1666.70  4950.7 1663.39  5001.2 1660.05
  5005.3 1658.62  5005.6 1658.12  5009.1 1658.12  5009.3 1658.62  5014.1 1660.59
  5036.9 1660.47  5057.0 1661.65  5087.0 1667.10  5095.4 1669.80  5100.4 1670.15
  5107.0 1672.00  5117.0 1672.94  5127.0 1674.79  5197.1 1682.99  5243.3 1686.05
#Mann=4,-1,0
  4732.0    0.07       0  4950.7     0.1       0  5005.3    0.05       0
  5009.3     0.1       0
Bank Sta=5005.3,5009.3
Exp/Cntr=0.3,0.1

Type RM Length L Ch R = 1,4140,447,447,447
BEGIN DESCRIPTION:
Stream0059 8.0
END DESCRIPTION:
XS GIS Cut Line= 4
      1973074.99     13909425.01      1973375.00     13909225.00
      1973387.87     13909156.34      1973274.37     13908963.37
#Sta/Elev= 30
  4635.1 1700.91  4638.1 1700.91  4663.7 1692.37  4671.2 1688.62  4720.7 1681.67
  4756.8 1675.18  4801.9 1669.33  4815.4 1666.38  4899.8 1657.74  4923.6 1656.94
  4952.1 1651.87  4973.1 1650.21  4998.2 1649.53  5014.0 1647.50  5014.3 1647.00
  5017.8 1647.00  5018.0 1647.50  5022.0 1649.31  5056.7 1649.72  5063.7 1650.80
  5069.2 1650.80  5082.8 1653.50  5098.4 1655.54  5104.2 1657.56  5141.4 1662.11
  5178.5 1663.93  5199.9 1666.54  5258.5 1671.14  5280.0 1674.50  5289.4 1675.13
#Mann=4,-1,0
  4635.1    0.07       0  4899.8     0.1       0  5014.0    0.05       0
  5018.0     0.1       0
Bank Sta=5014,5018
Exp/Cntr=0.3,0.1

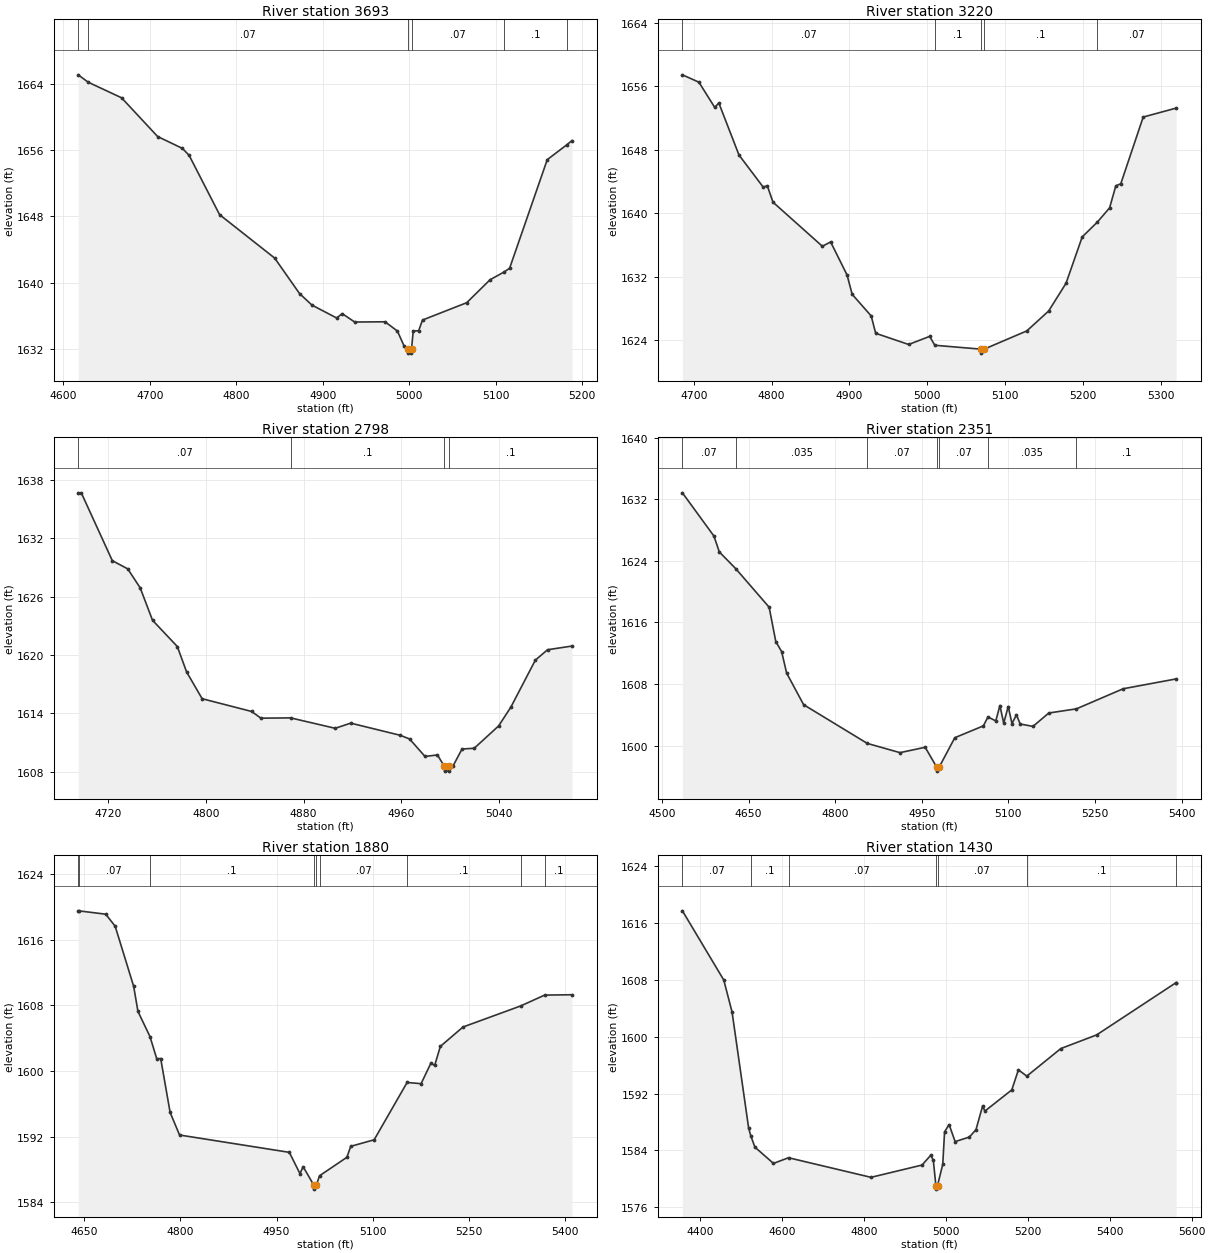
Type RM Length L Ch R = 1,3693,473,473,473
BEGIN DESCRIPTION:
Stream0059 7.0
END DESCRIPTION:
XS GIS Cut Line= 3
      1973475.00     13909625.00      1973775.00     13909375.00
      1973925.01     13909274.99
#Sta/Elev= 30
  4617.2 1665.05  4628.7 1664.16  4667.3 1662.28  4709.0 1657.61  4737.6 1656.18
  4745.4 1655.34  4780.6 1648.19  4844.3 1642.95  4873.0 1638.68  4887.3 1637.29
  4915.9 1635.73  4922.4 1636.25  4936.8 1635.24  4971.9 1635.27  4986.2 1634.15
  4994.0 1632.32  4998.5 1631.99  4998.8 1631.49  5002.3 1631.49  5002.5 1631.99
  5004.5 1634.18  5010.7 1634.18  5015.2 1635.48  5066.3 1637.57  5093.3 1640.34
  5109.6 1641.28  5115.9 1641.73  5159.4 1654.82  5182.1 1656.62  5188.0 1657.12
#Mann=6,-1,0
  4617.2   0.035       0  4628.7    0.07       0  4998.5    0.05       0
  5002.5    0.07       0  5109.6     0.1       0  5182.1    0.07       0
Bank Sta=4998.5,5002.5
Exp/Cntr=0.3,0.1

Type RM Length L Ch R = 1,3220,422,422,422
BEGIN DESCRIPTION:
Stream0059 6.0
END DESCRIPTION:
XS GIS Cut Line= 4
      1973674.98     13909724.99      1973882.43     13909796.73
      1973975.00     13909775.00      1974224.97     13909575.03
#Sta/Elev= 30
  4685.4 1657.43  4706.6 1656.50  4726.9 1653.33  4732.2 1653.88  4758.1 1647.33
  4789.2 1643.29  4794.5 1643.46  4801.8 1641.39  4865.3 1635.83  4875.9 1636.38
  4897.0 1632.22  4903.6 1629.78  4928.1 1627.05  4933.8 1624.87  4976.2 1623.46
  5003.2 1624.48  5009.8 1623.36  5069.2 1622.87  5069.5 1622.37  5073.2 1622.87
  5128.1 1625.17  5156.1 1627.67  5178.5 1631.17  5199.3 1637.01  5218.8 1638.88
  5234.5 1640.67  5242.5 1643.44  5248.9 1643.71  5277.7 1652.11  5320.1 1653.24
#Mann=5,-1,0
  4685.4    0.07       0  5009.8     0.1       0  5069.2    0.05       0
  5073.2     0.1       0  5218.8    0.07       0
Bank Sta=5069.2,5073.2
Exp/Cntr=0.3,0.1

Type RM Length L Ch R = 1,2798,447,447,447
BEGIN DESCRIPTION:
Stream0059 5.0
END DESCRIPTION:
XS GIS Cut Line= 3
      1973775.02     13910175.00      1974075.00     13910125.00
      1974174.98     13910125.00
#Sta/Elev= 30
  4695.5 1636.66  4698.0 1636.66  4723.4 1629.69  4736.0 1628.85  4746.2 1626.90
  4756.3 1623.57  4776.6 1620.87  4784.2 1618.26  4796.9 1615.51  4837.4 1614.20
  4845.0 1613.51  4869.3 1613.54  4905.8 1612.47  4918.5 1613.00  4959.1 1611.75
  4966.7 1611.37  4979.3 1609.58  4989.5 1609.73  4995.1 1608.57  4995.3 1608.07
  4998.8 1608.07  4999.1 1608.57  5002.1 1608.57  5009.6 1610.34  5019.6 1610.42
  5039.6 1612.72  5049.6 1614.65  5069.6 1619.47  5079.6 1620.54  5099.6 1620.92
#Mann=4,-1,0
  4695.5    0.07       0  4869.3     0.1       0  4995.1    0.05       0
  4999.1     0.1       0
Bank Sta=4995.1,4999.1
Exp/Cntr=0.3,0.1

Type RM Length L Ch R = 1,2351,471,471,471
BEGIN DESCRIPTION:
Stream0059 4.0
END DESCRIPTION:
XS GIS Cut Line= 4
      1973695.82     13910400.95      1974067.84     13910551.81
      1974125.00     13910525.00      1974375.00     13910224.99
#Sta/Elev= 30
  4535.5 1632.83  4590.1 1627.21  4599.4 1625.15  4627.6 1623.00  4685.7 1617.97
  4697.2 1613.51  4707.3 1612.21  4716.0 1609.41  4745.4 1605.31  4855.7 1600.28
  4912.3 1599.08  4955.9 1599.78  4976.0 1597.18  4976.2 1596.68  4980.0 1597.18
  5007.2 1601.02  5056.7 1602.56  5064.6 1603.72  5078.2 1603.20  5085.3 1605.20
  5091.9 1602.92  5099.7 1605.07  5106.2 1602.86  5114.0 1603.99  5120.5 1602.80
  5142.6 1602.49  5170.0 1604.23  5217.8 1604.77  5298.8 1607.38  5390.6 1608.66
#Mann=7,-1,0
  4535.5    0.07       0  4627.6   0.035       0  4855.7    0.07       0
  4976.0    0.05       0  4980.0    0.07       0  5064.6   0.035       0
  5217.8     0.1       0
Bank Sta=4976,4980
Exp/Cntr=0.3,0.1

Type RM Length L Ch R = 1,1880,450,450,450
BEGIN DESCRIPTION:
Stream0059 3.0
END DESCRIPTION:
XS GIS Cut Line= 4
      1973824.98     13910774.98      1974076.32     13910957.56
      1974161.25     13910963.17      1974479.47     13910765.29
#Sta/Elev= 30
  4640.6 1619.51  4641.2 1619.51  4683.5 1619.10  4698.2 1617.64  4727.1 1610.32
  4733.8 1607.26  4752.6 1604.19  4763.1 1601.50  4769.3 1601.52  4784.0 1594.96
  4798.7 1592.21  4970.0 1590.10  4986.6 1587.51  4991.6 1588.35  5008.1 1586.12
  5008.3 1585.62  5012.1 1586.12  5017.2 1587.25  5059.9 1589.50  5065.8 1590.83
  5102.4 1591.63  5153.8 1598.61  5175.6 1598.46  5190.9 1600.95  5196.8 1600.68
  5205.7 1603.00  5241.0 1605.36  5331.1 1607.93  5368.5 1609.25  5411.1 1609.29
#Mann=9,-1,0
  4640.6   0.035       0  4641.2    0.07       0  4752.6     0.1       0
  5008.1    0.05       0  5012.1     0.1       0  5017.2    0.07       0
  5153.8     0.1       0  5331.1    0.07       0  5368.5     0.1       0
Bank Sta=5008.1,5012.1
Exp/Cntr=0.3,0.1

Type RM Length L Ch R = 1,1430,471,471,471
BEGIN DESCRIPTION:
Stream0059 2.0
END DESCRIPTION:
XS GIS Cut Line= 4
      1973675.04     13911424.99      1974225.20     13911346.64
      1974275.00     13911275.00      1974543.61     13910780.96
#Sta/Elev= 30
  4357.0 1617.73  4458.0 1607.98  4478.2 1603.48  4518.6 1587.16  4524.0 1586.03
  4534.0 1584.46  4579.2 1582.17  4616.0 1582.97  4817.3 1580.21  4941.9 1581.94
  4963.4 1583.33  4969.5 1582.60  4975.7 1579.05  4975.9 1578.55  4979.7 1579.05
  4992.5 1582.05  4996.9 1586.61  5008.0 1587.64  5022.7 1585.24  5057.4 1585.88
  5073.6 1586.92  5089.7 1590.24  5095.4 1589.54  5161.0 1592.52  5177.2 1595.34
  5197.7 1594.46  5280.7 1598.34  5368.1 1600.26  5561.2 1607.59  5562.3 1607.59
#Mann=7,-1,0
  4357.0    0.07       0  4524.0     0.1       0  4616.0    0.07       0
  4975.7    0.05       0  4979.7    0.07       0  5197.7     0.1       0
  5561.2   0.035       0
Bank Sta=4975.7,4979.7
Exp/Cntr=0.3,0.1

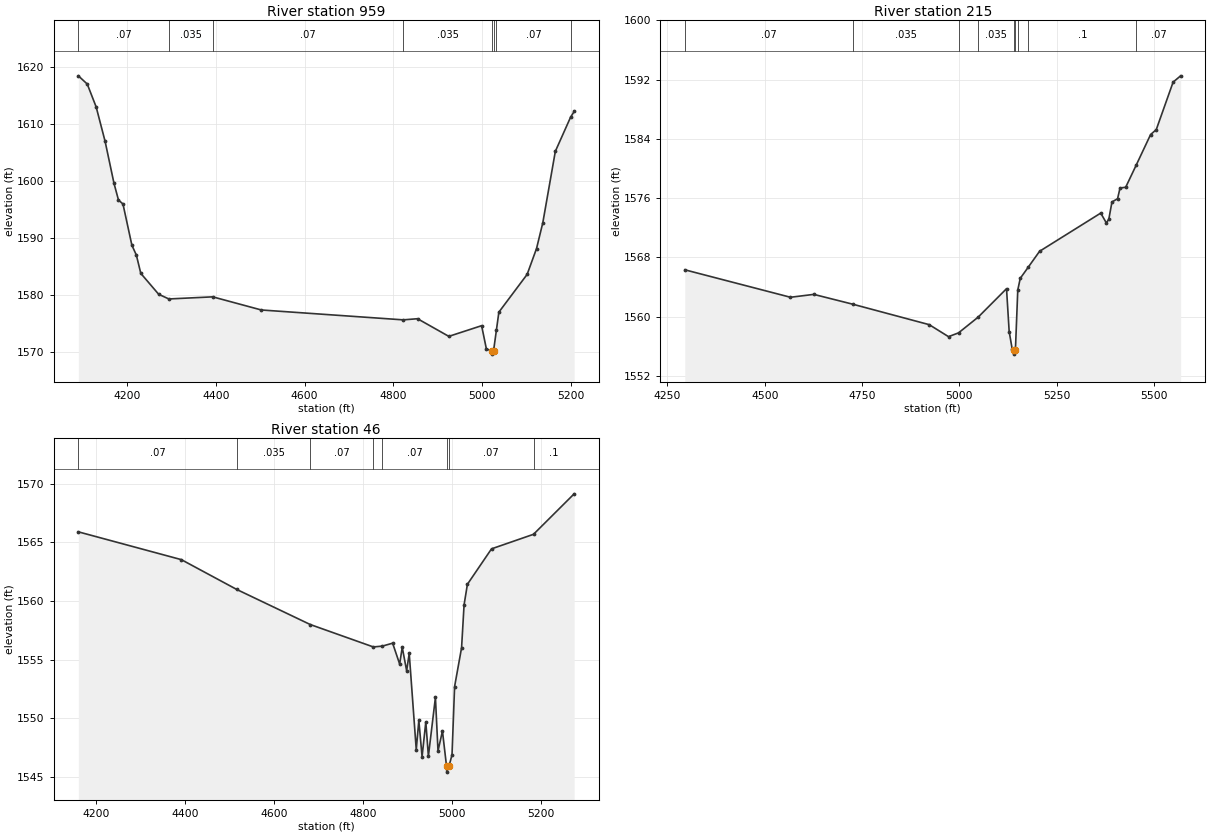
Type RM Length L Ch R = 1,959,744,744,744
BEGIN DESCRIPTION:
Stream0059 1.0
END DESCRIPTION:
XS GIS Cut Line= 3
      1973625.05     13911525.01      1974525.00     13911625.00
      1974674.98     13911475.02
#Sta/Elev= 30
  4089.9 1618.37  4110.0 1616.93  4130.1 1612.92  4150.2 1606.91  4170.3 1599.54
  4180.4 1596.62  4190.5 1595.93  4210.6 1588.71  4220.7 1586.98  4230.7 1583.78
  4271.0 1580.12  4294.0 1579.30  4392.8 1579.67  4502.4 1577.37  4822.2 1575.64
  4854.5 1575.84  4925.0 1572.75  4998.9 1574.62  5009.5 1570.61  5021.7 1570.14
  5021.9 1569.64  5025.7 1570.14  5032.4 1573.93  5037.8 1576.99  5101.5 1583.60
  5122.7 1588.13  5136.8 1592.63  5165.1 1605.15  5199.3 1611.10  5207.5 1612.13
#Mann=8,-1,0
  4089.9    0.07       0  4294.0   0.035       0  4392.8    0.07       0
  4822.2   0.035       0  5021.7   0.035       0  5025.7   0.035       0
  5032.4    0.07       0  5199.3     0.1       0
Bank Sta=5021.7,5025.7
Exp/Cntr=0.3,0.1

Type RM Length L Ch R = 1,215,169,169,169
BEGIN DESCRIPTION:
Stream0059 0.0
END DESCRIPTION:
XS GIS Cut Line= 3
      1974383.68     13912212.39      1974931.56     13912202.85
      1975499.99     13911751.81
#Sta/Elev= 30
  4294.6 1566.31  4566.0 1562.60  4626.0 1562.99  4727.0 1561.65  4922.4 1558.90
  4972.0 1557.28  4997.7 1557.79  5048.2 1559.92  5121.0 1563.76  5127.8 1557.97
  5135.5 1555.62  5139.8 1555.42  5140.1 1554.92  5143.8 1555.42  5149.9 1563.58
  5156.3 1565.16  5177.3 1566.70  5205.9 1568.81  5363.0 1573.97  5377.4 1572.64
  5383.8 1573.15  5391.8 1575.47  5406.2 1575.91  5412.6 1577.36  5427.1 1577.46
  5454.3 1580.47  5491.1 1584.58  5505.6 1585.24  5548.9 1591.66  5568.2 1592.51
#Mann=9,-1,0
  4294.6    0.07       0  4727.0   0.035       0  4997.7    0.07       0
  5048.2   0.035       0  5139.8    0.05       0  5143.8   0.035       0
  5149.9    0.07       0  5177.3     0.1       0  5454.3    0.07       0
Bank Sta=5139.8,5143.8
Exp/Cntr=0.3,0.1

Type RM Length L Ch R = 1,46,0,0,0
BEGIN DESCRIPTION:
Stream0059 0.2
END DESCRIPTION:
XS GIS Cut Line= 4
      1974394.93     13912269.96      1974947.23     13912333.98
      1975219.58     13912176.64      1975333.53     13911960.69
#Sta/Elev= 30
  4160.5 1565.90  4392.1 1563.53  4516.6 1560.99  4681.9 1558.00  4823.7 1556.09
  4843.9 1556.16  4867.1 1556.41  4882.9 1554.63  4888.7 1556.06  4898.6 1554.06
  4904.4 1555.54  4920.2 1547.33  4926.0 1549.83  4933.3 1546.74  4941.7 1549.70
  4947.5 1546.78  4963.3 1551.79  4969.1 1547.23  4979.1 1548.92  4988.3 1545.92
  4988.8 1545.42  4993.8 1545.92  5000.6 1546.90  5006.4 1552.71  5022.1 1556.02
  5027.7 1559.67  5035.2 1561.43  5089.4 1564.45  5183.8 1565.69  5275.2 1569.14
#Mann=8,-1,0
  4160.5    0.07       0  4516.6   0.035       0  4681.9    0.07       0
  4823.7   0.035       0  4843.9    0.07       0  4988.3    0.05       0
  4993.8    0.07       0  5183.8     0.1       0
Bank Sta=4988.3,4993.8
Exp/Cntr=0.3,0.1

Chan Stop Cuts=-1