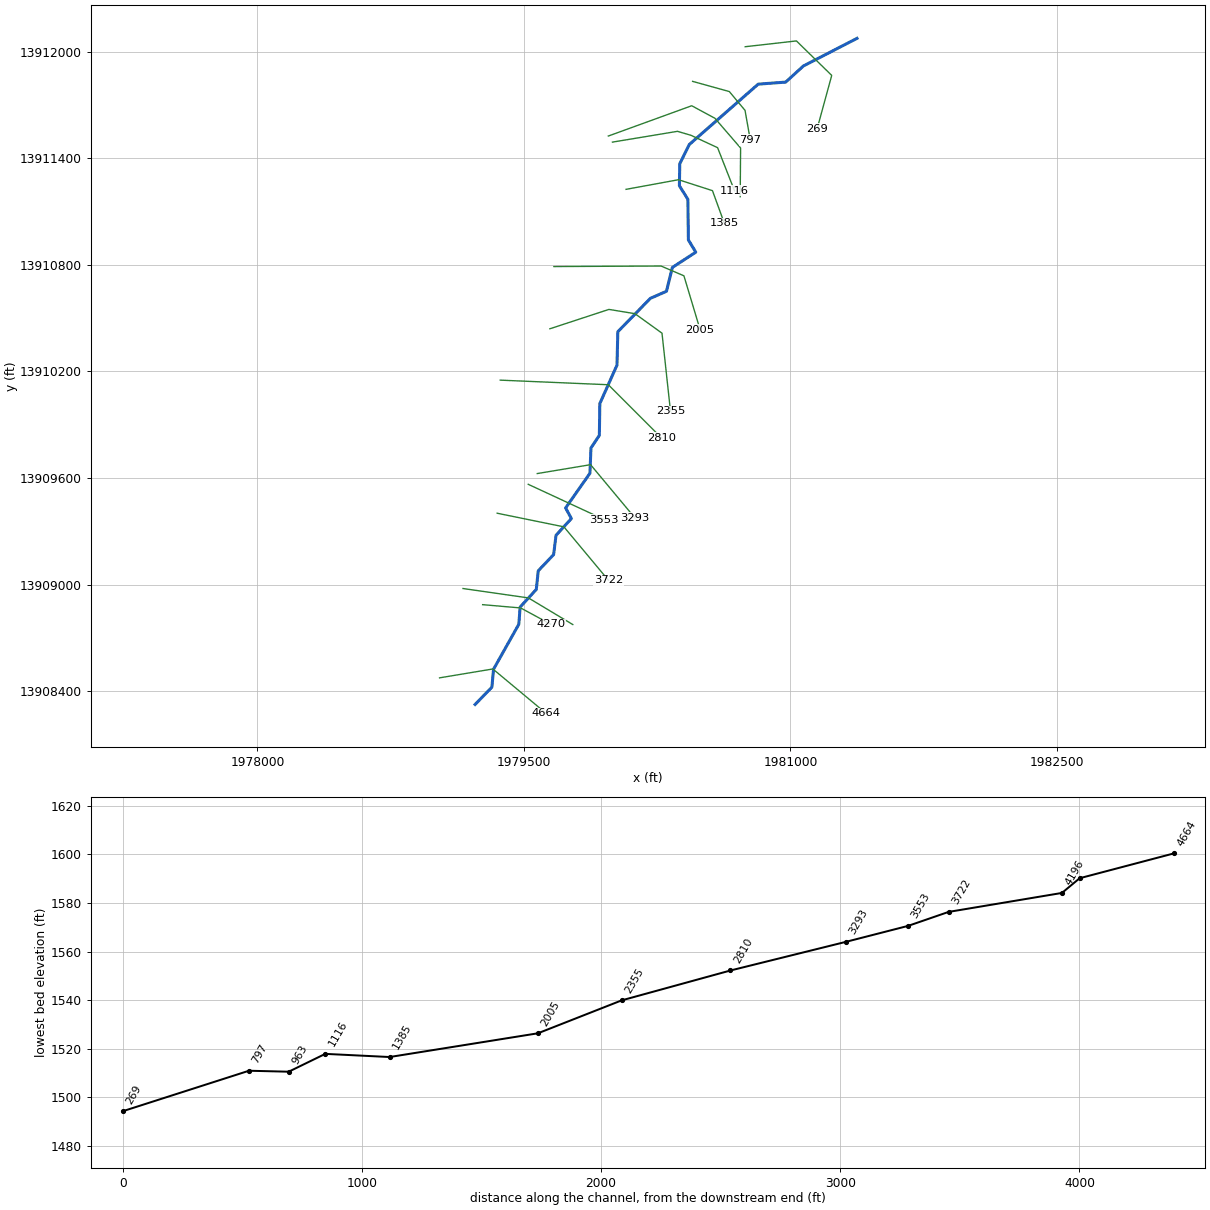
--- Stream0060.prj (project) ---

Proj Title=Stream0060 Base Level Engineering
Current Plan=p01
Default Exp/Contr=0.3,0.1
English Units
Geom File=g01
Flow File=f01
Plan File=p01
BEGIN DESCRIPTION:
Stream0060
END DESCRIPTION:

--- Stream0060.p01 (plan) ---

Plan Title=Multiple Run
Short Identifier=Multiple
Geom File=g01
Flow File=f01
Subcritical Flow
K Sum by GR= 0
Std Step Tol= 0.01
Critical Tol= 0.01
Num of Std Step Trials= 20
Max Error Tol= 0.3
Flow Tol Ratio= 0.001
Split Flow NTrial= 30
Split Flow Tol= 0.02
Split Flow Ratio= 0.02
Log Output Level= 0
Friction Slope Method= 1
Unsteady Friction Slope Method= 2
Unsteady Bridges Friction Slope Method= 1
Parabolic Critical Depth
Global Vel Dist=  1 , 1 , 1
Global Log Level= 0
CheckData=True
Encroach Param= -1, 0, 0, 0
BEGIN DESCRIPTION:
Multiple Run
END DESCRIPTION:

--- Stream0060.f01 (steady flow) ---

Flow Title=Multiple
Number of Profiles=7
Profile Names=10-year,25-year,50-year,1pct_min,100-year,1pct_plu,500-year
River Rch & RM= Stream0060,Reach-1,4664
     560     918    1248     824    1644    3280    2819
Boundary for River Rch & Prof#=Stream0060,Reach-1,1
Up Type=0
Dn Type=3
Dn Slope=0.005
Boundary for River Rch & Prof#=Stream0060,Reach-1,2
Up Type=0
Dn Type=3
Dn Slope=0.005
Boundary for River Rch & Prof#=Stream0060,Reach-1,3
Up Type=0
Dn Type=3
Dn Slope=0.005
Boundary for River Rch & Prof#=Stream0060,Reach-1,4
Up Type=0
Dn Type=3
Dn Slope=0.005
Boundary for River Rch & Prof#=Stream0060,Reach-1,5
Up Type=0
Dn Type=3
Dn Slope=0.005
Boundary for River Rch & Prof#=Stream0060,Reach-1,6
Up Type=0
Dn Type=3
Dn Slope=0.005
Boundary for River Rch & Prof#=Stream0060,Reach-1,7
Up Type=0
Dn Type=3
Dn Slope=0.005

--- Stream0060.g01 (geometry) ---

Geom Title=Existing Conditions

River Reach=Stream0060,Reach-1
Reach XY= 30
      1979225.00     13908325.00      1979319.54     13908422.55
      1979328.83     13908523.41      1979471.17     13908776.59
      1979478.62     13908873.50      1979569.46     13908972.58
      1979580.54     13909077.42      1979667.12     13909168.84
      1979680.55     13909277.43      1979766.99     13909371.67
      1979734.59     13909431.55      1979871.45     13909626.47
      1979877.27     13909769.06      1979924.48     13909840.22
      1979927.26     13910019.06      1980023.78     13910235.50
      1980028.54     13910423.54      1980211.80     13910611.36
      1980302.28     13910651.11      1980335.39     13910785.10
      1980467.31     13910871.33      1980425.67     13910940.15
      1980422.74     13911169.06      1980375.05     13911245.04
      1980377.23     13911369.07      1980430.83     13911477.30
      1980818.81     13911817.18      1980973.53     13911828.55
      1981072.71     13911919.15      1981375.00     13912075.00

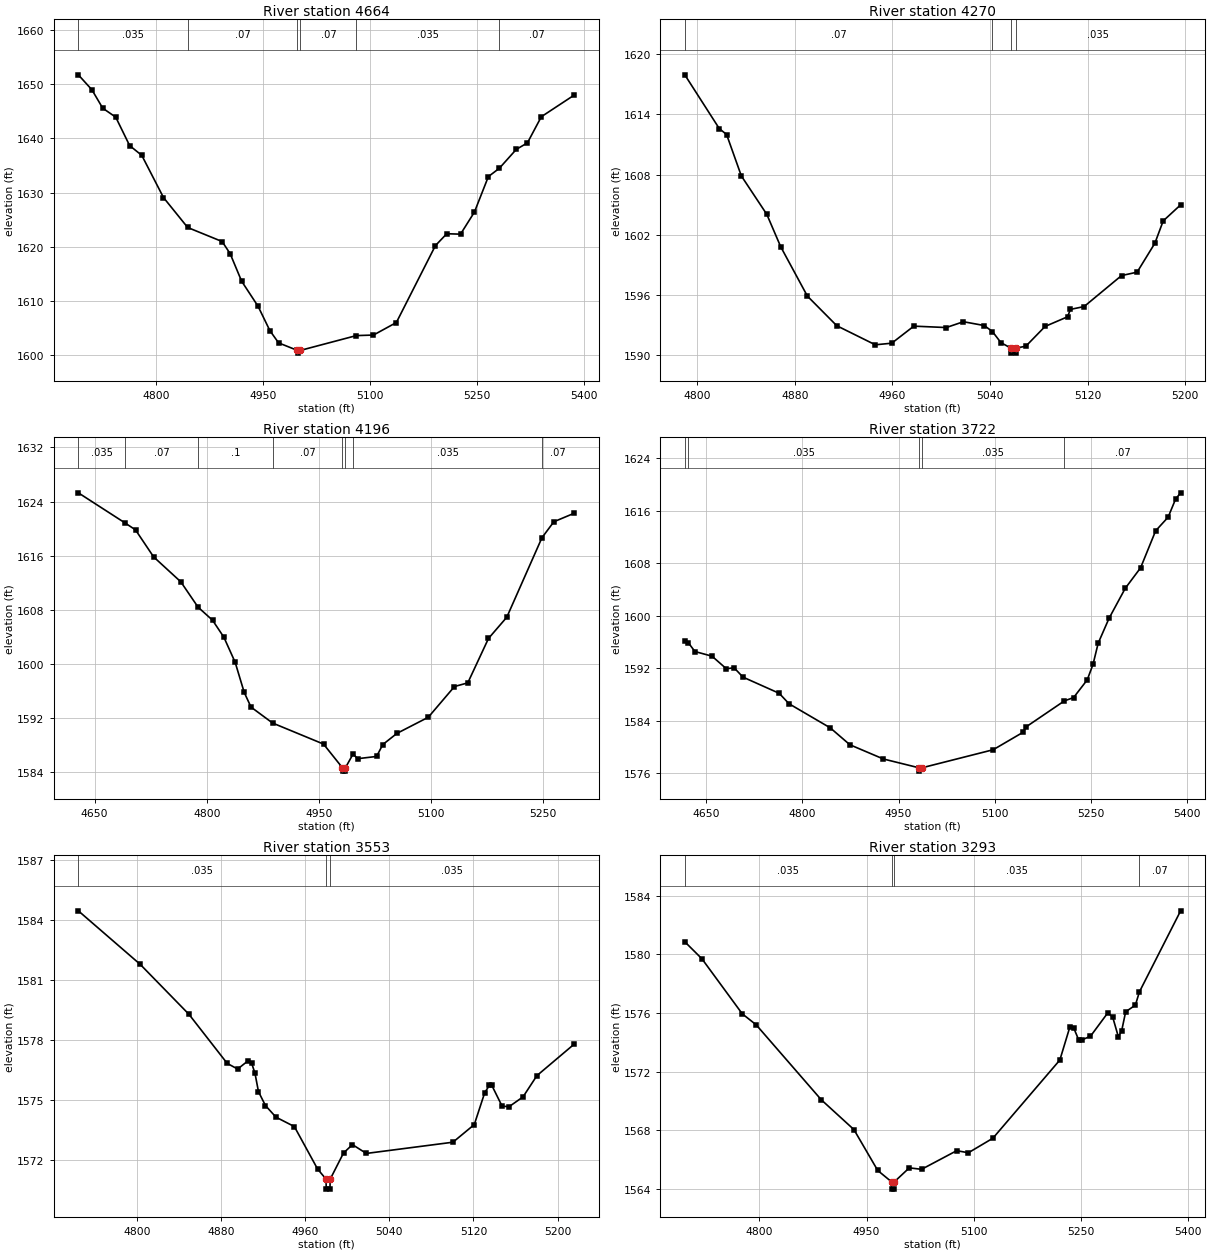
Type RM Length L Ch R = 1,4664,394,394,394
BEGIN DESCRIPTION:
Stream0060 9.0
END DESCRIPTION:
XS GIS Cut Line= 3
      1979024.97     13908474.99      1979325.00     13908525.00
      1979625.01     13908274.99
#Sta/Elev= 30
  4691.4 1651.71  4710.4 1648.96  4725.6 1645.56  4743.8 1643.91  4763.3 1638.67
  4780.3 1636.87  4810.7 1629.10  4844.6 1623.58  4892.9 1620.99  4904.1 1618.76
  4920.2 1613.68  4943.2 1609.07  4959.8 1604.57  4972.0 1602.32  4998.4 1600.93
  4998.6 1600.43  5002.4 1600.93  5080.9 1603.66  5104.9 1603.76  5137.0 1606.07
  5191.7 1620.24  5207.6 1622.43  5226.9 1622.35  5246.4 1626.43  5265.9 1632.96
  5281.2 1634.48  5305.0 1637.97  5320.6 1639.17  5340.1 1643.99  5386.1 1647.97
#Mann=6,-1,0
  4691.4   0.035       0  4844.6    0.07       0  4998.4    0.05       0
  5002.4    0.07       0  5080.9   0.035       0  5281.2    0.07       0
Bank Sta=4998.4,5002.4
Exp/Cntr=0.3,0.1

Type RM Length L Ch R = 1,4270,74,74,74
BEGIN DESCRIPTION:
Mapping XS 2a78878b
END DESCRIPTION:
XS GIS Cut Line= 3
      1979267.49     13908886.98      1979481.69     13908868.46
      1979650.27     13908776.98
#Sta/Elev= 30
  4789.6 1617.94  4817.9 1612.58  4823.9 1611.99  4836.0 1607.86  4856.9 1604.03
  4868.3 1600.80  4890.2 1595.88  4914.3 1592.93  4945.9 1591.03  4959.4 1591.19
  4977.5 1592.89  5004.1 1592.75  5018.2 1593.33  5035.3 1592.95  5042.0 1592.35
  5049.0 1591.24  5057.2 1590.70  5057.5 1590.20  5061.0 1590.20  5061.2 1590.70
  5069.4 1590.89  5085.2 1592.86  5103.6 1593.82  5106.0 1594.56  5117.2 1594.84
  5147.9 1597.93  5160.7 1598.27  5175.3 1601.16  5182.1 1603.38  5196.4 1604.98
#Mann=4,-1,0
  4789.6    0.07       0  5042.0   0.035       0  5057.2    0.05       0
  5061.2   0.035       0
Bank Sta=5057.2,5061.2
Exp/Cntr=0.3,0.1

Type RM Length L Ch R = 1,4196,474,474,474
BEGIN DESCRIPTION:
Stream0060 8.0
END DESCRIPTION:
XS GIS Cut Line= 3
      1979156.98     13908977.81      1979525.00     13908925.00
      1979774.97     13908775.02
#Sta/Elev= 30
  4628.2 1625.29  4690.5 1620.85  4704.7 1619.81  4728.9 1615.82  4765.3 1612.13
  4788.4 1608.38  4807.7 1606.46  4822.9 1603.94  4838.0 1600.23  4850.1 1595.78
  4859.2 1593.61  4888.1 1591.25  4956.2 1588.14  4981.5 1584.64  4981.8 1584.14
  4985.3 1584.14  4985.5 1584.64  4995.7 1586.66  5001.9 1585.98  5027.2 1586.31
  5035.5 1588.07  5054.4 1589.72  5096.4 1592.11  5131.4 1596.65  5149.2 1597.19
  5176.9 1603.76  5201.4 1606.90  5248.4 1618.65  5264.3 1621.01  5291.5 1622.27
#Mann=8,-1,0
  4628.2   0.035       0  4690.5    0.07       0  4788.4     0.1       0
  4888.1    0.07       0  4981.5   0.035       0  4985.5    0.07       0
  4995.7   0.035       0  5248.4    0.07       0
Bank Sta=4981.5,4985.5
Exp/Cntr=0.3,0.1

Type RM Length L Ch R = 1,3722,169,169,169
BEGIN DESCRIPTION:
Stream0060 7.0
END DESCRIPTION:
XS GIS Cut Line= 3
      1979349.23     13909401.75      1979725.00     13909325.00
      1979974.98     13909025.03
#Sta/Elev= 30
  4616.4 1596.12  4622.0 1595.88  4632.2 1594.55  4658.9 1593.84  4681.2 1591.93
  4693.4 1592.07  4707.2 1590.65  4763.8 1588.18  4779.1 1586.59  4843.4 1582.92
  4874.1 1580.34  4926.4 1578.17  4982.3 1576.82  4982.5 1576.32  4986.3 1576.82
  5097.8 1579.58  5144.4 1582.24  5149.4 1583.08  5209.0 1587.03  5223.3 1587.53
  5244.6 1590.23  5253.7 1592.61  5261.7 1595.82  5278.7 1599.62  5304.0 1604.19
  5327.9 1607.31  5351.4 1612.95  5370.9 1615.03  5382.6 1617.80  5390.4 1618.74
#Mann=5,-1,0
  4616.4    0.07       0  4622.0   0.035       0  4982.3   0.035       0
  4986.3   0.035       0  5209.0    0.07       0
Bank Sta=4982.3,4986.3
Exp/Cntr=0.3,0.1

Type RM Length L Ch R = 1,3553,260,260,260
BEGIN DESCRIPTION:
Mapping XS f1b2d03d
END DESCRIPTION:
XS GIS Cut Line= 2
      1979524.34     13909564.38      1979951.81     13909366.14
#Sta/Elev= 30
  4744.5 1584.45  4803.3 1581.78  4849.6 1579.29  4886.0 1576.84  4895.9 1576.56
  4905.8 1576.97  4909.1 1576.87  4912.4 1576.34  4915.7 1575.43  4922.3 1574.74
  4932.3 1574.16  4949.8 1573.69  4971.9 1571.57  4979.9 1571.07  4980.1 1570.57
  4983.6 1570.57  4983.9 1571.07  4996.5 1572.37  5005.0 1572.79  5018.2 1572.35
  5100.5 1572.91  5120.8 1573.79  5130.7 1575.38  5135.2 1575.75  5137.3 1575.76
  5147.2 1574.71  5153.8 1574.68  5167.1 1575.17  5180.3 1576.23  5215.7 1577.80
#Mann=3,-1,0
  4744.5   0.035       0  4979.9   0.035       0  4983.9   0.035       0
Bank Sta=4979.9,4983.9
Exp/Cntr=0.3,0.1

Type RM Length L Ch R = 1,3293,483,483,483
BEGIN DESCRIPTION:
Stream0060 6.0
END DESCRIPTION:
XS GIS Cut Line= 3
      1979575.04     13909625.01      1979875.00     13909675.00
      1980124.99     13909375.01
#Sta/Elev= 30
  4695.4 1580.85  4719.4 1579.69  4775.9 1575.94  4795.4 1575.19  4886.6 1570.08
  4932.3 1568.05  4965.7 1565.26  4985.0 1564.49  4985.3 1563.99  4988.8 1563.99
  4989.0 1564.49  5009.9 1565.44  5027.1 1565.34  5076.3 1566.61  5092.7 1566.47
  5127.0 1567.46  5220.8 1572.79  5235.0 1575.07  5240.3 1574.97  5247.4 1574.14
  5252.0 1574.17  5263.7 1574.41  5288.2 1576.02  5295.0 1575.69  5302.8 1574.37
  5307.4 1574.78  5313.0 1576.08  5326.6 1576.53  5332.3 1577.44  5390.0 1582.96
#Mann=4,-1,0
  4695.4   0.035       0  4985.0   0.035       0  4989.0   0.035       0
  5332.3    0.07       0
Bank Sta=4985,4989
Exp/Cntr=0.3,0.1

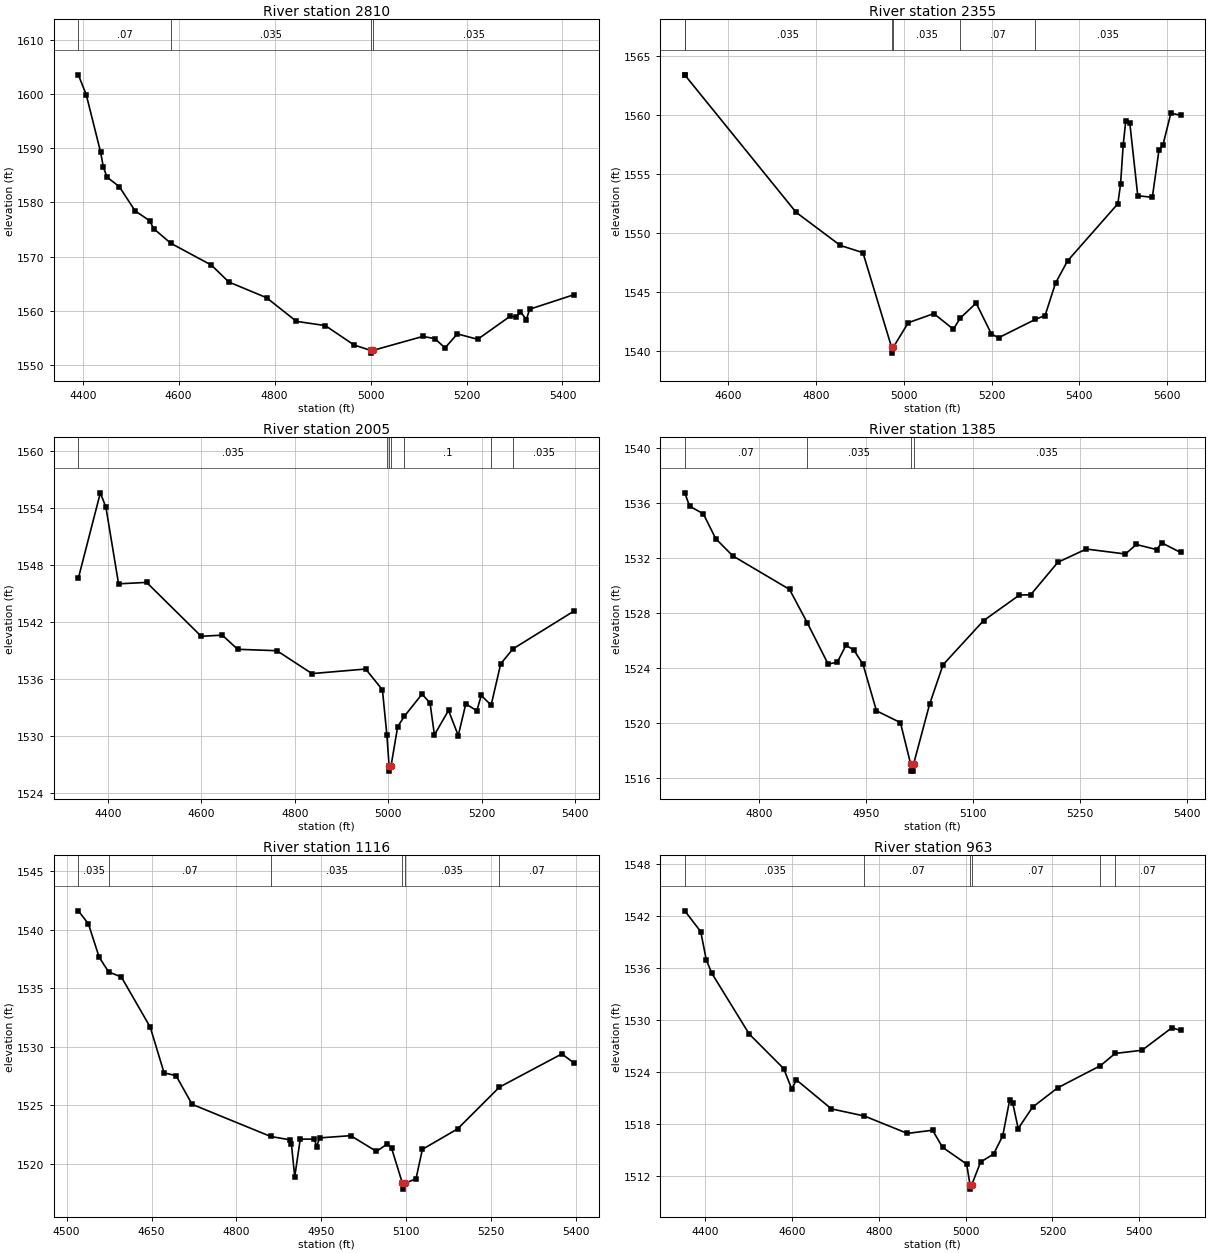
Type RM Length L Ch R = 1,2810,455,455,455
BEGIN DESCRIPTION:
Stream0060 5.0
END DESCRIPTION:
XS GIS Cut Line= 3
      1979366.45     13910150.84      1979975.00     13910125.00
      1980275.03     13909824.97
#Sta/Elev= 30
  4390.9 1603.53  4407.3 1599.89  4437.2 1589.31  4443.2 1586.45  4450.9 1584.63
  4476.2 1582.91  4509.2 1578.43  4539.3 1576.62  4548.3 1575.11  4583.7 1572.45
  4668.4 1568.41  4704.4 1565.31  4783.3 1562.40  4845.5 1558.04  4905.6 1557.26
  4965.6 1553.68  5000.6 1552.68  5000.8 1552.18  5004.6 1552.68  5108.9 1555.26
  5133.9 1554.86  5155.1 1553.14  5180.8 1555.73  5223.2 1554.73  5291.1 1559.00
  5303.6 1558.85  5312.3 1559.81  5324.8 1558.38  5331.4 1560.28  5424.3 1562.97
#Mann=4,-1,0
  4390.9    0.07       0  4583.7   0.035       0  5000.6   0.035       0
  5004.6   0.035       0
Bank Sta=5000.6,5004.6
Exp/Cntr=0.3,0.1

Type RM Length L Ch R = 1,2355,350,350,350
BEGIN DESCRIPTION:
Stream0060 4.0
END DESCRIPTION:
XS GIS Cut Line= 5
      1979645.95     13910439.97      1979978.34     13910549.04
      1980125.00     13910525.00      1980277.18     13910415.22
      1980325.00     13909975.00
#Sta/Elev= 30
  4501.6 1563.38  4501.8 1563.36  4755.0 1551.76  4855.8 1548.96  4907.2 1548.35
  4972.4 1540.36  4972.6 1539.86  4976.4 1540.36  5010.3 1542.43  5068.7 1543.20
  5113.1 1541.88  5128.8 1542.82  5164.9 1544.09  5199.8 1541.47  5216.1 1541.16
  5299.7 1542.71  5321.9 1543.04  5345.8 1545.79  5373.0 1547.65  5487.5 1552.48
  5493.7 1554.12  5499.7 1557.45  5505.7 1559.51  5514.8 1559.30  5532.9 1553.16
  5566.1 1553.03  5581.2 1557.01  5590.2 1557.44  5608.3 1560.14  5630.5 1559.96
#Mann=6,-1,0
  4501.6    0.07       0  4501.8   0.035       0  4972.4   0.035       0
  4976.4   0.035       0  5128.8    0.07       0  5299.7   0.035       0
Bank Sta=4972.4,4976.4
Exp/Cntr=0.3,0.1

Type RM Length L Ch R = 1,2005,620,620,620
BEGIN DESCRIPTION:
Stream0060 3.0
END DESCRIPTION:
XS GIS Cut Line= 4
      1979668.61     13910790.31      1980271.93     13910793.16
      1980400.49     13910738.29      1980492.09     13910433.57
#Sta/Elev= 30
  4336.6 1546.62  4383.7 1555.63  4395.7 1554.10  4422.7 1546.04  4482.7 1546.19
  4599.7 1540.51  4644.7 1540.63  4677.7 1539.14  4761.7 1538.99  4836.7 1536.58
  4951.6 1537.06  4987.5 1534.87  4997.0 1530.13  5001.8 1526.80  5002.1 1526.30
  5005.8 1526.80  5020.1 1530.98  5034.3 1532.07  5072.3 1534.42  5089.4 1533.48
  5098.8 1530.12  5129.0 1532.70  5149.8 1530.05  5166.0 1533.39  5189.6 1532.66
  5199.0 1534.28  5220.2 1533.25  5240.7 1537.61  5266.8 1539.18  5397.9 1543.18
#Mann=7,-1,0
  4336.6   0.035       0  4997.0    0.07       0  5001.8    0.05       0
  5005.8    0.07       0  5034.3     0.1       0  5220.2    0.07       0
  5266.8   0.035       0
Bank Sta=5001.8,5005.8
Exp/Cntr=0.3,0.1

Type RM Length L Ch R = 1,1385,269,269,269
BEGIN DESCRIPTION:
Stream0060 2.0
END DESCRIPTION:
XS GIS Cut Line= 4
      1980074.97     13911224.99      1980370.20     13911279.09
      1980561.20     13911217.58      1980627.94     13911034.15
#Sta/Elev= 30
  4695.3 1536.72  4702.0 1535.75  4721.3 1535.20  4738.6 1533.40  4762.5 1532.15
  4842.3 1529.71  4867.5 1527.26  4896.5 1524.29  4909.4 1524.43  4921.6 1525.66
  4932.6 1525.31  4945.5 1524.27  4964.3 1520.90  4998.0 1520.04  5012.4 1517.02
  5012.7 1516.52  5016.2 1516.52  5016.4 1517.02  5038.9 1521.37  5057.8 1524.24
  5114.6 1527.44  5165.0 1529.30  5180.8 1529.32  5219.0 1531.68  5258.9 1532.64
  5313.8 1532.28  5329.1 1532.97  5357.6 1532.60  5364.8 1533.09  5391.3 1532.39
#Mann=4,-1,0
  4695.3    0.07       0  4867.5   0.035       0  5012.4   0.035       0
  5016.4   0.035       0
Bank Sta=5012.4,5016.4
Exp/Cntr=0.3,0.1

Type RM Length L Ch R = 1,1116,153,153,153
BEGIN DESCRIPTION:
Stream0060 1.1
END DESCRIPTION:
XS GIS Cut Line= 5
      1979998.08     13911490.74      1980364.38     13911551.50
      1980440.77     13911528.93      1980590.08     13911459.49
      1980685.58     13911216.40
#Sta/Elev= 30
  4520.6 1541.61  4538.4 1540.50  4557.4 1537.65  4574.3 1536.38  4596.6 1535.96
  4647.8 1531.66  4672.2 1527.76  4693.4 1527.52  4721.8 1525.07  4860.8 1522.32
  4894.2 1522.04  4897.3 1521.71  4903.3 1518.88  4913.0 1522.09  4938.0 1522.10
  4941.9 1521.45  4947.4 1522.20  5002.2 1522.39  5047.7 1521.05  5067.2 1521.68
  5074.4 1521.34  5093.7 1518.32  5093.9 1517.82  5097.7 1518.32  5117.7 1518.70
  5129.0 1521.22  5191.3 1522.97  5265.3 1526.54  5375.7 1529.38  5397.4 1528.59
#Mann=6,-1,0
  4520.6   0.035       0  4574.3    0.07       0  4860.8   0.035       0
  5093.7   0.035       0  5097.7   0.035       0  5265.3    0.07       0
Bank Sta=5093.7,5097.7
Exp/Cntr=0.3,0.1

Type RM Length L Ch R = 1,963,166,166,166
BEGIN DESCRIPTION:
Stream0060 1.0
END DESCRIPTION:
XS GIS Cut Line= 5
      1979975.04     13911525.01      1980444.52     13911695.56
      1980575.00     13911625.00      1980719.58     13911457.59
      1980717.41     13911183.63
#Sta/Elev= 30
  4352.4 1542.59  4389.2 1540.18  4401.9 1536.93  4414.7 1535.38  4500.9 1528.37
  4580.4 1524.38  4599.1 1522.00  4609.4 1523.09  4690.4 1519.73  4766.4 1518.91
  4865.6 1516.90  4923.6 1517.27  4946.5 1515.30  5002.1 1513.36  5009.9 1510.97
  5010.1 1510.47  5013.9 1510.97  5034.3 1513.60  5064.1 1514.51  5085.3 1516.62
  5101.2 1520.72  5108.2 1520.44  5121.0 1517.46  5154.1 1519.93  5212.2 1522.17
  5310.6 1524.72  5344.5 1526.13  5406.5 1526.50  5475.4 1529.10  5495.4 1528.78
#Mann=6,-1,0
  4352.4   0.035       0  4766.4    0.07       0  5009.9    0.05       0
  5013.9    0.07       0  5310.6     0.1       0  5344.5    0.07       0
Bank Sta=5009.9,5013.9
Exp/Cntr=0.3,0.1

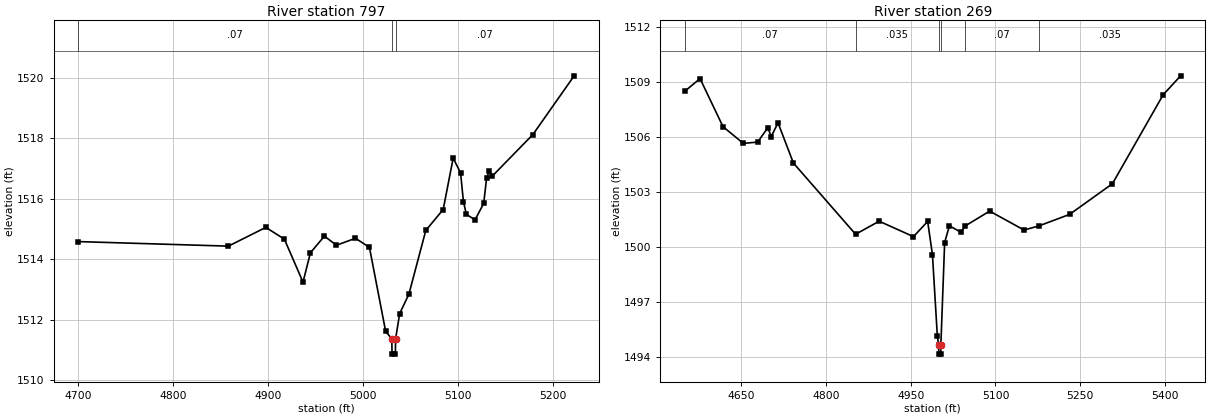
Type RM Length L Ch R = 1,797,528,528,528
BEGIN DESCRIPTION:
Mapping XS 547cf3b1
END DESCRIPTION:
XS GIS Cut Line= 4
      1980449.46     13911832.75      1980656.05     13911775.46
      1980744.59     13911669.56      1980774.11     13911502.88
#Sta/Elev= 30
  4700.5 1514.59  4858.4 1514.44  4897.8 1515.06  4917.3 1514.67  4936.9 1513.25
  4944.7 1514.22  4959.4 1514.77  4972.1 1514.47  4992.1 1514.70  5006.8 1514.40
  5023.8 1511.63  5030.3 1511.37  5030.6 1510.87  5034.1 1510.87  5034.3 1511.37
  5038.6 1512.21  5048.3 1512.85  5066.1 1514.96  5084.4 1515.65  5094.9 1517.35
  5102.7 1516.86  5105.7 1515.91  5108.8 1515.49  5117.9 1515.31  5127.0 1515.85
  5130.1 1516.69  5133.1 1516.94  5136.2 1516.76  5178.8 1518.13  5222.2 1520.07
#Mann=3,-1,0
  4700.5    0.07       0  5030.3    0.05       0  5034.3    0.07       0
Bank Sta=5030.3,5034.3
Exp/Cntr=0.3,0.1

Type RM Length L Ch R = 1,269,0,0,0
BEGIN DESCRIPTION:
Stream0060 0.0
END DESCRIPTION:
XS GIS Cut Line= 4
      1980745.45     13912027.82      1981033.97     13912060.39
      1981232.55     13911866.27      1981150.73     13911566.79
#Sta/Elev= 30
  4549.6 1508.50  4576.6 1509.19  4617.3 1506.57  4653.3 1505.66  4678.6 1505.73
  4696.7 1506.51  4702.7 1506.03  4714.8 1506.78  4742.0 1504.59  4852.2 1500.71
  4894.0 1501.42  4954.8 1500.58  4979.9 1501.41  4988.4 1499.59  4997.0 1495.19
  4999.3 1494.68  4999.6 1494.18  5003.1 1494.18  5003.3 1494.68  5010.0 1500.26
  5018.4 1501.17  5039.4 1500.81  5045.7 1501.15  5089.7 1501.97  5150.7 1500.94
  5177.5 1501.17  5231.3 1501.79  5307.2 1503.46  5397.2 1508.31  5428.1 1509.34
#Mann=6,-1,0
  4549.6    0.07       0  4852.2   0.035       0  4999.3   0.035       0
  5003.3   0.035       0  5045.7    0.07       0  5177.5   0.035       0
Bank Sta=4999.3,5003.3
Exp/Cntr=0.3,0.1

Chan Stop Cuts=-1