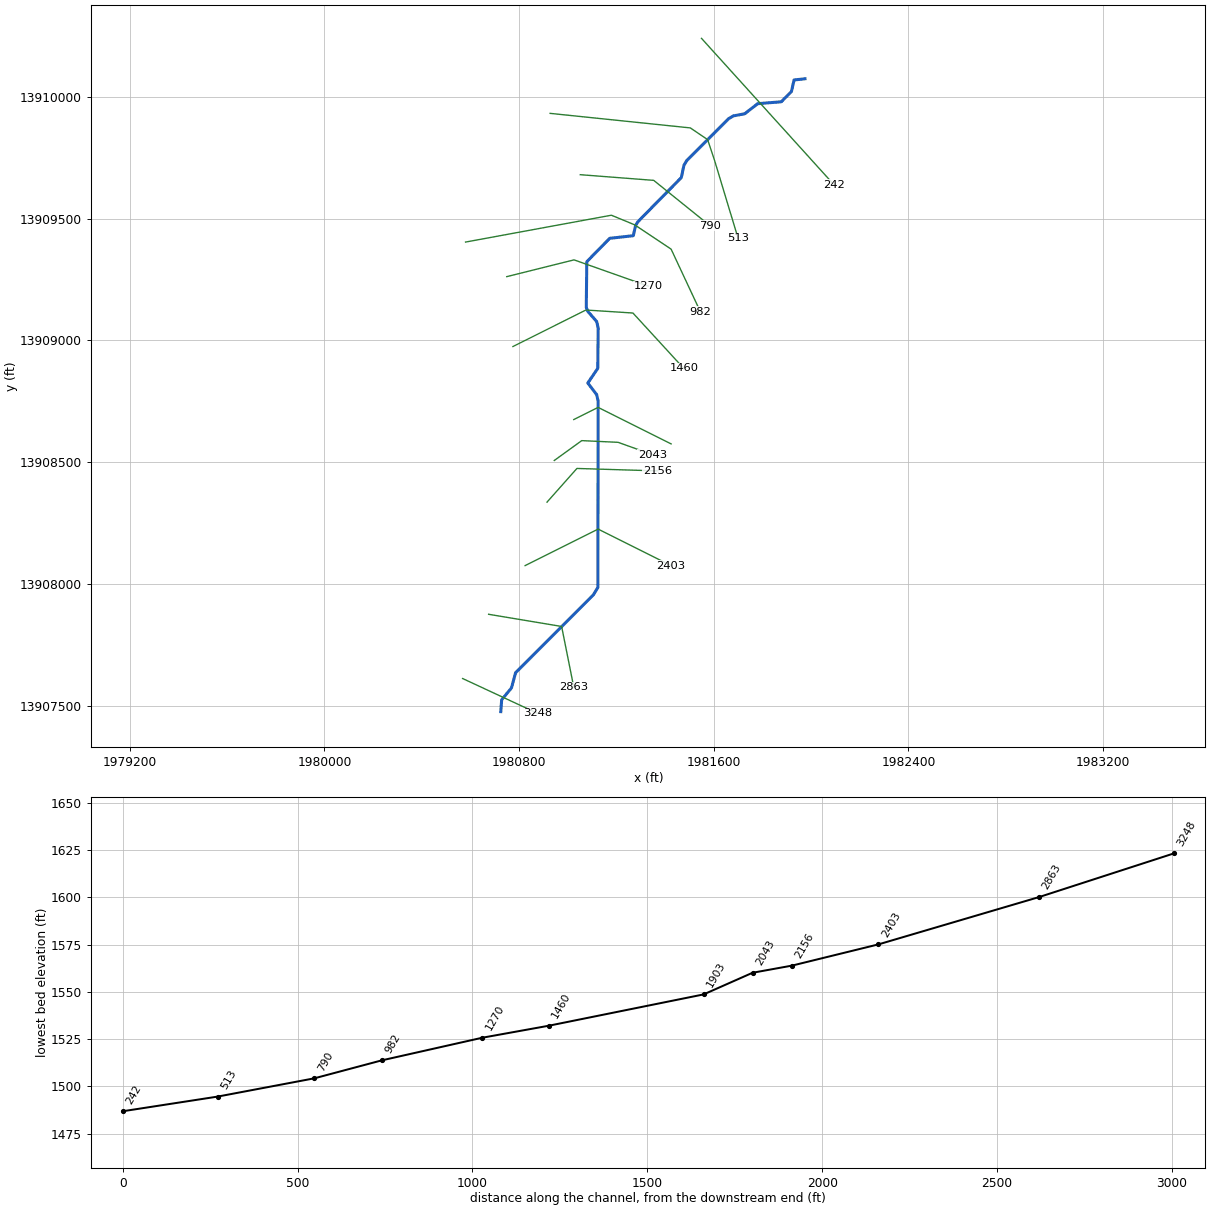
--- Stream0061.prj (project) ---

Proj Title=Stream0061 Base Level Engineering
Current Plan=p01
Default Exp/Contr=0.3,0.1
English Units
Geom File=g01
Flow File=f01
Plan File=p01
Y Axis Title=Elevation
X Axis Title(PF)=Main Channel Distance
X Axis Title(XS)=Station
BEGIN DESCRIPTION:
Stream0061
END DESCRIPTION:
DSS Export Rating Curves= 0
DSS Export Rating Curve Sorted= 0
DSS Export Volume Flow Curves= 0
DXF OffsetX= 0
DXF OffsetY= 0
DXF ScaleX= 1
DXF ScaleY= 10

--- Stream0061.p01 (plan) ---

Plan Title=Multiple Run
Short Identifier=Multiple
Geom File=g01
Flow File=f01
Subcritical Flow
K Sum by GR= 0
Std Step Tol= 0.01
Critical Tol= 0.01
Num of Std Step Trials= 20
Max Error Tol= 0.3
Flow Tol Ratio= 0.001
Split Flow NTrial= 30
Split Flow Tol= 0.02
Split Flow Ratio= 0.02
Log Output Level= 0
Friction Slope Method= 1
Unsteady Friction Slope Method= 2
Unsteady Bridges Friction Slope Method= 1
Parabolic Critical Depth
Global Vel Dist=  1 , 1 , 1
Global Log Level= 0
CheckData=True
Encroach Param= -1, 0, 0, 0
BEGIN DESCRIPTION:
Multiple Run
END DESCRIPTION:

--- Stream0061.f01 (steady flow) ---

Flow Title=Multiple
Number of Profiles=7
Profile Names=10-year,25-year,50-year,1pct_min,100-year,1pct_plu,500-year
River Rch & RM= Stream0061,Reach-1,3248
     379     611     821     538    1074    2143    1811
Boundary for River Rch & Prof#=Stream0061,Reach-1,1
Up Type=0
Dn Type=3
Dn Slope=0.005
Boundary for River Rch & Prof#=Stream0061,Reach-1,2
Up Type=0
Dn Type=3
Dn Slope=0.005
Boundary for River Rch & Prof#=Stream0061,Reach-1,3
Up Type=0
Dn Type=3
Dn Slope=0.005
Boundary for River Rch & Prof#=Stream0061,Reach-1,4
Up Type=0
Dn Type=3
Dn Slope=0.005
Boundary for River Rch & Prof#=Stream0061,Reach-1,5
Up Type=0
Dn Type=3
Dn Slope=0.005
Boundary for River Rch & Prof#=Stream0061,Reach-1,6
Up Type=0
Dn Type=3
Dn Slope=0.005
Boundary for River Rch & Prof#=Stream0061,Reach-1,7
Up Type=0
Dn Type=3
Dn Slope=0.005

--- Stream0061.g01 (geometry) ---

Geom Title=Existing Conditions
Program Version=4.10

River Reach=Stream0061      ,Reach-1
Reach XY= 30
        1980725.       13907475.       1980728.6     13907523.51
      1980769.03     13907572.76      1980785.75     13907634.69
       1981105.4     13907954.84      1981123.95     13907985.43
      1981125.11     13908750.12      1981118.98     13908777.45
      1981082.56       13908825.      1981123.62     13908885.44
       1981125.2     13909050.08      1981119.25     13909077.33
      1981083.14     13909118.94      1981076.22     13909135.51
      1981078.53     13909323.55      1981172.62     13909419.46
      1981269.53     13909430.26      1981279.15     13909472.92
      1981288.74     13909487.95      1981466.84     13909668.95
      1981477.53     13909718.95      1981488.63     13909738.21
      1981661.78     13909911.38      1981681.03      13909922.5
      1981727.17     13909931.14      1981780.97     13909972.67
      1981877.67     13909980.42      1981919.42     13910022.54
      1981930.35     13910070.04        1981975.       13910075.

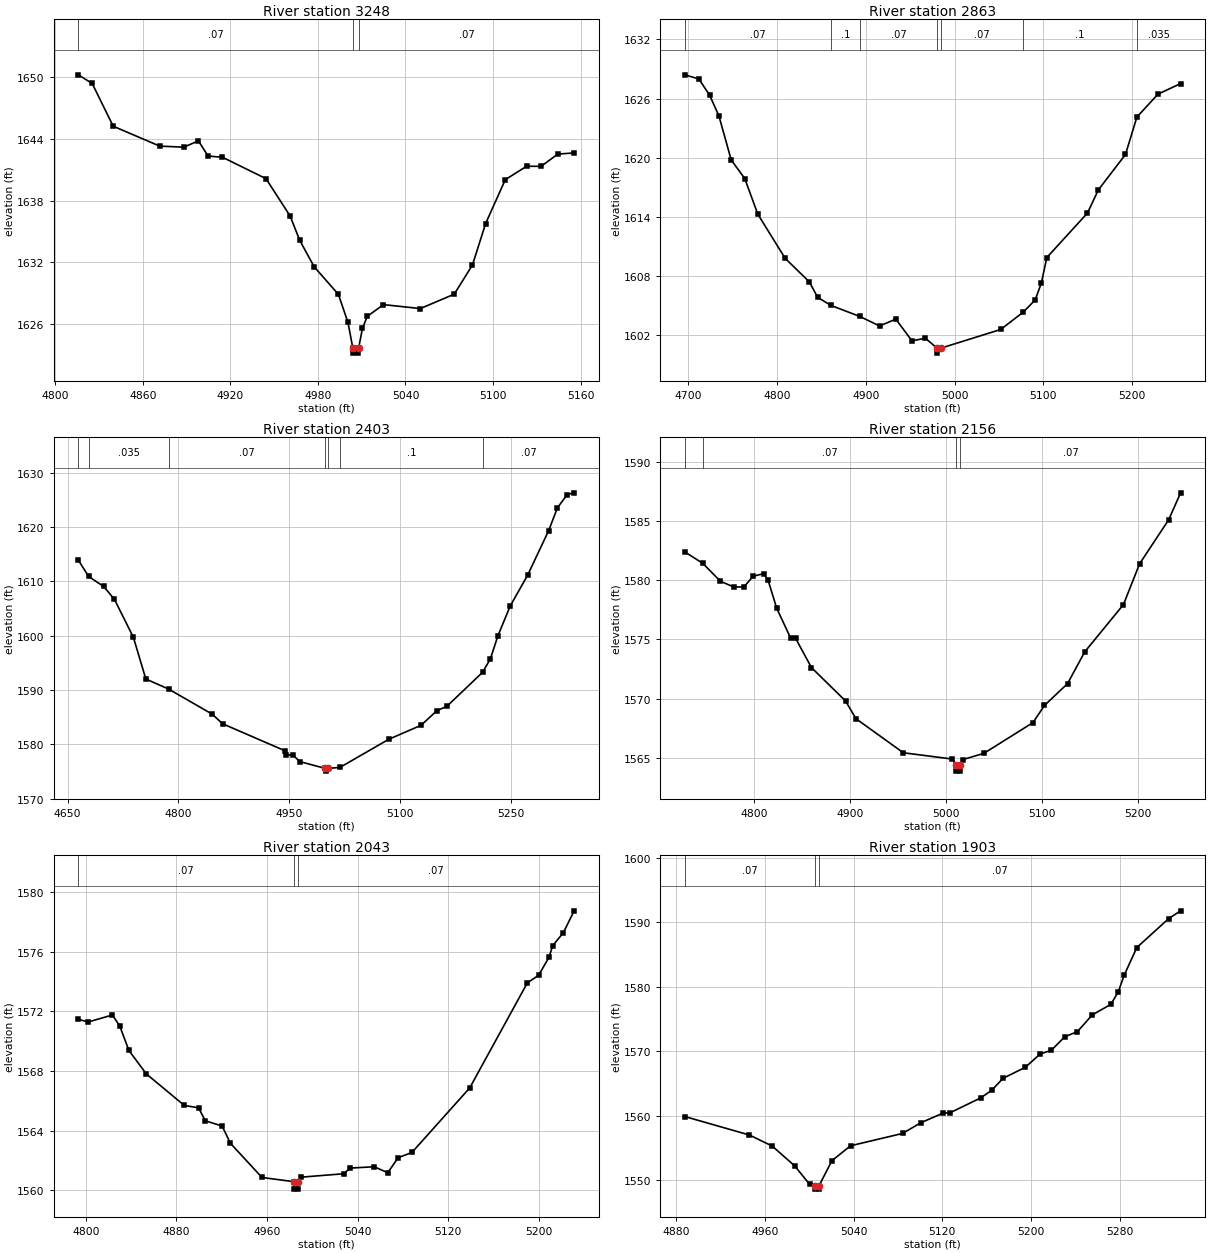
Type RM Length L Ch R = 1 ,3248    ,385,385,385
BEGIN DESCRIPTION:
Stream0061 7.0
END DESCRIPTION:
XS GIS Cut Line= 2
      1980568.09     13907611.15      1980876.23     13907467.93
#Sta/Elev= 30
  4815.8 1650.18  4825.3 1649.34  4839.7  1645.2  4871.6 1643.27  4888.1 1643.17
  4898.1 1643.78  4904.7 1642.31  4914.6 1642.19  4944.4 1640.12  4960.9 1636.51
  4967.5 1634.15  4977.4 1631.58    4994 1628.91  5000.6 1626.18  5003.9 1623.71
  5004.2 1623.21  5007.7 1623.21  5007.9 1623.71  5010.5  1625.6  5013.8 1626.77
  5024.9 1627.91  5050.2 1627.53  5073.4 1628.92  5085.9 1631.75  5094.9 1635.76
  5108.4 1640.02    5123 1641.32  5132.9 1641.31  5144.4  1642.5  5155.6 1642.61
#Mann= 3 ,-1 , 0
  4815.8     .07       0  5003.9     .05       0  5007.9     .07       0
Bank Sta=5003.9,5007.9
XS Rating Curve= 0 ,0
Exp/Cntr=0.3,0.1

Type RM Length L Ch R = 1 ,2863    ,460,460,460
BEGIN DESCRIPTION:
Stream0061 6.0
END DESCRIPTION:
XS GIS Cut Line= 3
      1980675.04     13907874.99        1980975.       13907825.
      1981024.99     13907575.04
#Sta/Elev= 30
  4695.9 1628.41  4711.8 1627.99  4723.9 1626.34  4734.4 1624.23  4748.2 1619.77
  4763.5 1617.88  4778.2 1614.26  4809.1 1609.77  4836.4 1607.38  4845.6 1605.82
  4860.8 1604.99  4893.3 1603.87  4915.5 1602.91  4933.8  1603.6    4952  1601.4
  4967.2 1601.66  4980.4 1600.65  4980.7 1600.15  4984.4 1600.65    5052 1602.55
  5077.6 1604.32  5090.9 1605.55  5097.9 1607.27    5104 1609.85  5149.9 1614.38
  5162.1 1616.72  5192.7 1620.32  5205.6 1624.12  5229.4 1626.45  5254.9 1627.52
#Mann= 7 ,-1 , 0
  4695.9     .07       0  4860.8      .1       0  4893.3     .07       0
  4980.4     .05       0  4984.4     .07       0  5077.6      .1       0
  5205.6    .035       0
Bank Sta=4980.4,4984.4
XS Rating Curve= 0 ,0
Exp/Cntr=0.3,0.1

Type RM Length L Ch R = 1 ,2403    ,247,247,247
BEGIN DESCRIPTION:
Stream0061 5.0
END DESCRIPTION:
XS GIS Cut Line= 3
      1980825.02     13908075.01        1981125.       13908225.
        1981425.       13908075.
#Sta/Elev= 30
  4664.6 1613.92  4678.5 1610.92  4698.9 1609.07  4713.5 1606.69  4739.1 1599.71
  4755.9 1592.05  4786.9 1590.18  4845.5 1585.59  4859.9  1583.8  4943.9 1578.85
  4946.1 1578.08    4955 1578.05  4964.3 1576.84  4998.7 1575.59    4999 1575.09
  5002.7 1575.59  5018.6 1575.78  5084.6 1580.95  5128.2 1583.52  5149.8 1586.23
  5163.2 1587.02  5211.5 1593.28  5222.1 1595.76  5232.2 1599.98    5249 1605.52
  5272.4 1611.14  5300.9 1619.35  5312.7 1623.54  5326.1    1626  5335.4 1626.31
#Mann= 7 ,-1 , 0
  4664.6     .07       0  4678.5    .035       0  4786.9     .07       0
  4998.7     .05       0  5002.7     .07       0  5018.6      .1       0
  5211.5     .07       0
Bank Sta=4998.7,5002.7
XS Rating Curve= 0 ,0
Exp/Cntr=0.3,0.1

Type RM Length L Ch R = 1 ,2156    ,113,113,113
BEGIN DESCRIPTION:
Mapping XS 9e739852
END DESCRIPTION:
XS GIS Cut Line= 3
      1980915.05     13908335.73       1981037.9     13908474.12
       1981369.5     13908463.98
#Sta/Elev= 30
  4727.8 1582.39  4746.6 1581.42  4764.9 1579.91  4778.7 1579.43  4789.4 1579.43
  4799.1 1580.34  4810.1 1580.55  4814.6    1580  4823.6 1577.63  4838.2 1575.09
  4843.2  1575.1  4859.8 1572.62  4895.3  1569.8  4906.2  1568.3  4955.6 1565.42
  5006.7 1564.89  5010.7 1564.37  5010.9 1563.87  5014.4 1563.87  5014.7 1564.37
  5017.8 1564.85  5039.5 1565.37  5090.7 1567.97  5102.7 1569.42  5126.7 1571.26
  5144.7 1573.95    5185 1577.94  5201.8 1581.38  5232.1  1585.1  5244.6 1587.38
#Mann= 4 ,-1 , 0
  4727.8    .035       0  4746.6     .07       0  5010.7     .05       0
  5014.7     .07       0
Bank Sta=5010.7,5014.7
XS Rating Curve= 0 ,0
Exp/Cntr=0.3,0.1

Type RM Length L Ch R = 1 ,2043    ,140,140,140
BEGIN DESCRIPTION:
Stream0061 3.2
END DESCRIPTION:
XS GIS Cut Line= 4
       1980944.8     13908506.81      1981057.65     13908588.42
      1981206.96     13908581.47      1981347.58     13908531.13
#Sta/Elev= 30
  4793.3 1571.46    4802 1571.28  4823.4 1571.75  4829.9 1571.01    4838 1569.37
  4853.4  1567.8  4886.9 1565.69  4899.5 1565.53  4905.5 1564.66  4920.3 1564.31
  4927.7 1563.15  4955.6 1560.86  4983.7 1560.58  4983.9 1560.08  4987.4 1560.08
  4987.7 1560.58  4989.9 1560.88  5027.7 1561.11  5033.7 1561.49  5054.7 1561.58
  5066.7 1561.18  5075.8 1562.18  5088.1 1562.54  5139.1 1566.86  5190.1 1573.91
    5200 1574.41  5209.2 1575.62  5212.4 1576.39  5221.9 1577.27  5231.4 1578.73
#Mann= 3 ,-1 , 0
  4793.3     .07       0  4983.7     .05       0  4987.7     .07       0
Bank Sta=4983.7,4987.7
XS Rating Curve= 0 ,0
Exp/Cntr=0.3,0.1

Type RM Length L Ch R = 1 ,1903    ,443,443,443
BEGIN DESCRIPTION:
Stream0061 4.0
END DESCRIPTION:
XS GIS Cut Line= 3
      1981024.99     13908674.99        1981125.       13908725.
      1981424.98     13908575.01
#Sta/Elev= 30
  4887.8 1559.88    4946 1557.02  4966.6 1555.31    4987 1552.22  5000.4 1549.36
  5004.8 1549.13  5005.1 1548.63  5008.6 1548.63  5008.8 1549.13  5020.5 1553.04
  5037.3 1555.35  5084.2 1557.26  5100.7 1558.92  5120.9 1560.42    5127 1560.46
  5154.7 1562.77  5164.7 1563.96  5174.8  1565.8  5194.9 1567.51  5208.3 1569.57
  5218.4 1570.14  5230.4 1572.23  5241.9 1573.04  5255.3 1575.63  5272.1 1577.27
  5278.8 1579.22  5284.1 1581.79  5295.5 1586.07  5324.3 1590.57    5335 1591.76
#Mann= 3 ,-1 , 0
  4887.8     .07       0  5004.8     .05       0  5008.8     .07       0
Bank Sta=5004.8,5008.8
XS Rating Curve= 0 ,0
Exp/Cntr=0.3,0.1

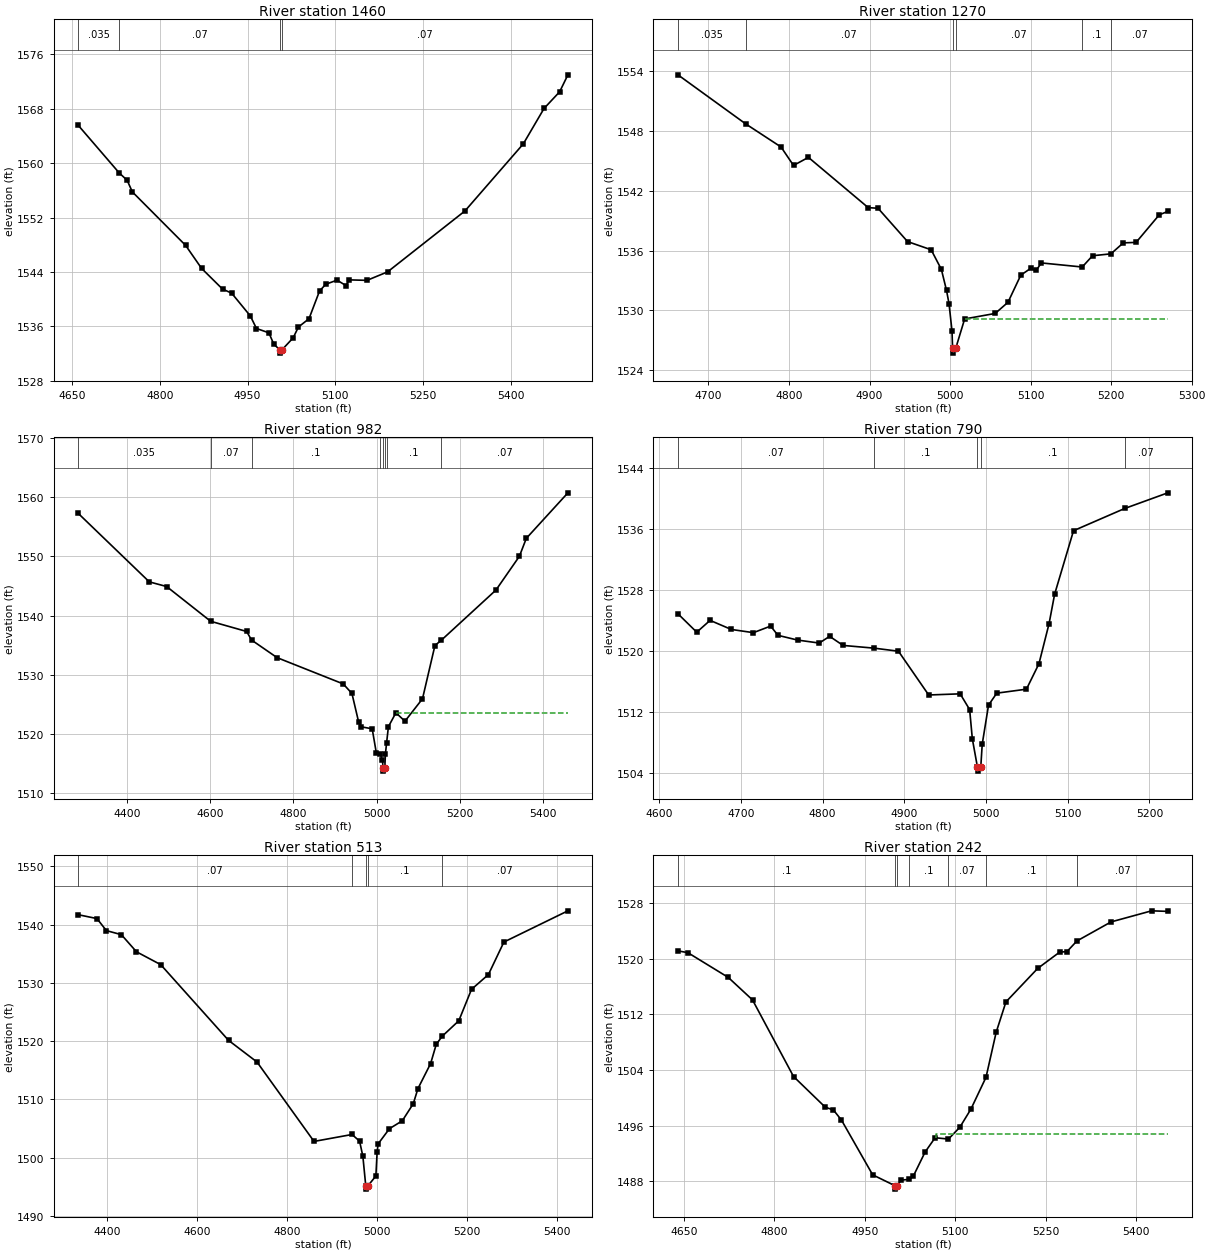
Type RM Length L Ch R = 1 ,1460    ,190,190,190
BEGIN DESCRIPTION:
Stream0061 3.0
END DESCRIPTION:
XS GIS Cut Line= 4
      1980775.04     13908975.02        1981075.       13909125.
      1981268.13     13909112.61      1981477.27     13908884.73
#Sta/Elev= 30
  4659.9 1565.59  4730.3 1558.56  4743.9 1557.48  4752.8 1555.77    4844  1547.9
  4871.3 1544.52  4907.1 1541.48  4922.7 1540.88  4954.7 1537.53  4965.2 1535.68
  4986.4 1535.05  4994.9 1533.37    5005 1532.56  5005.2 1532.06    5009 1532.56
    5028 1534.31    5037  1535.9  5055.1 1537.12  5073.1 1541.19  5083.8 1542.19
  5103.1 1542.79  5118.2    1542  5124.2 1542.83  5154.3 1542.76  5189.6 1544.01
    5322 1552.97  5421.8 1562.83  5457.3 1568.04  5483.9 1570.48  5498.1 1572.98
#Mann= 4 ,-1 , 0
  4659.9    .035       0  4730.3     .07       0    5005     .05       0
    5009     .07       0
Bank Sta=5005,5009
XS Rating Curve= 0 ,0
Exp/Cntr=0.3,0.1

Type RM Length L Ch R = 1 ,1270    ,288,288,288
BEGIN DESCRIPTION:
Mapping XS 27992cf8
END DESCRIPTION:
XS GIS Cut Line= 3
      1980749.45     13909262.08      1981026.06     13909330.99
       1981330.8     13909223.22
#Sta/Elev= 30
  4662.1 1553.64    4746 1548.73  4790.1  1546.4  4805.6 1544.55  4824.1 1545.36
  4898.3 1540.32  4910.6 1540.25  4947.2 1536.91  4976.5 1536.09  4989.2 1534.12
  4995.6 1532.01  4998.7 1530.68  5002.4 1527.94  5003.1 1526.22  5003.3 1525.72
  5007.1 1526.22  5018.1 1529.15    5056  1529.7  5071.9 1530.82  5087.8 1533.54
    5100 1534.22  5106.9 1534.01  5113.3 1534.77  5164.1 1534.36  5176.9 1535.49
  5199.7 1535.68  5215.1 1536.78    5231 1536.83  5259.7 1539.59  5270.4 1539.94
#Mann= 6 ,-1 , 0
  4662.1    .035       0    4746     .07       0  5003.1     .05       0
  5007.1     .07       0  5164.1      .1       0  5199.7     .07       0
#XS Ineff= 2 , 0
                         5018.67         1529.17
Permanent Ineff=
       F       F
Bank Sta=5003.1,5007.1
XS Rating Curve= 0 ,0
Exp/Cntr=0.3,0.1

Type RM Length L Ch R = 1 ,982     ,192,192,192
BEGIN DESCRIPTION:
Stream0061 2.0
END DESCRIPTION:
XS GIS Cut Line= 5
      1980580.17     13909404.11      1981179.55     13909514.43
        1981275.       13909475.        1981425.       13909375.
      1981545.51      13909117.4
#Sta/Elev= 30
  4282.5 1557.29  4453.8 1545.69  4495.5  1544.9  4601.3 1539.03  4687.7 1537.31
  4699.6 1535.86  4760.9 1532.89  4919.9 1528.45  4940.8 1526.84    4957 1521.99
  4963.5  1521.2  4989.5 1520.87  4999.6 1516.73  5009.1 1516.53  5014.1 1515.57
  5015.7 1514.22  5015.9 1513.72  5019.7 1514.22  5021.3 1516.62    5024 1518.42
  5028.5 1521.23  5046.5 1523.58  5068.2 1522.15  5110.4 1525.94  5140.3 1534.94
  5155.6 1535.83    5287 1544.31  5343.3 1550.01  5359.9 1553.04  5459.9 1560.73
#Mann= 8 ,-1 , 0
  4282.5    .035       0  4601.3     .07       0  4699.6      .1       0
  5009.1     .07       0  5015.7     .05       0  5019.7     .07       0
    5024      .1       0  5155.6     .07       0
#XS Ineff= 2 , 0
                         5047.55         1523.53
Permanent Ineff=
       F       F
Bank Sta=5015.7,5019.7
XS Rating Curve= 0 ,0
Exp/Cntr=0.3,0.1

Type RM Length L Ch R = 1 ,790     ,277,277,277
BEGIN DESCRIPTION:
Mapping XS eb72ace4
END DESCRIPTION:
XS GIS Cut Line= 3
      1981051.66     13909680.91       1981353.5     13909657.62
      1981584.51     13909471.49
#Sta/Elev= 30
  4623.1 1524.86  4646.1 1522.45  4662.4    1524  4688.4 1522.81  4715.4 1522.39
  4736.5 1523.25  4745.5 1522.04  4769.5 1521.42    4796 1521.03  4808.7 1521.91
  4825.1 1520.72  4863.3 1520.36  4892.9 1519.96  4929.9 1514.23  4968.4 1514.38
    4980 1512.32  4983.3 1508.49  4989.6 1504.76  4989.8 1504.26  4993.6 1504.76
  4995.4 1507.79  5003.1  1512.9  5013.2 1514.47  5049.5 1514.99  5064.8 1518.32
  5077.2 1523.58    5084 1527.43  5107.1 1535.74  5169.7 1538.65  5222.5  1540.7
#Mann= 5 ,-1 , 0
  4623.1     .07       0  4863.3      .1       0  4989.6     .05       0
  4993.6      .1       0  5169.7     .07       0
Bank Sta=4989.6,4993.6
XS Rating Curve= 0 ,0
Exp/Cntr=0.3,0.1

Type RM Length L Ch R = 1 ,513     ,271,271,271
BEGIN DESCRIPTION:
Stream0061 1.0
END DESCRIPTION:
XS GIS Cut Line= 5
       1980927.9     13909932.83      1981503.81     13909873.13
        1981575.       13909825.      1981603.99     13909738.03
      1981700.12     13909419.83
#Sta/Elev= 30
  4335.1  1541.7  4377.1 1541.03  4398.2 1538.96  4431.4 1538.27    4465 1535.33
  4518.9 1533.12  4669.7 1520.12    4733  1516.4  4859.7 1502.77  4944.2 1503.96
    4961 1502.82  4968.3 1500.21  4974.8 1495.08    4975 1494.58  4978.8 1495.08
  4997.2 1496.83    5000 1500.95  5002.1 1502.34  5027.4 1504.96  5055.9 1506.31
  5080.4 1509.25  5090.7 1511.84  5118.9 1516.14  5131.4 1519.43  5144.5 1520.82
  5181.5 1523.48  5209.8 1528.88  5247.4 1531.42  5281.8    1537  5424.1 1542.36
#Mann= 5 ,-1 , 0
  4335.1     .07       0  4944.2      .1       0  4974.8     .05       0
  4978.8      .1       0  5144.5     .07       0
Bank Sta=4974.8,4978.8
XS Rating Curve= 0 ,0
Exp/Cntr=0.3,0.1

Type RM Length L Ch R = 1 ,242     ,0,0,0
BEGIN DESCRIPTION:
Stream0061 0.0
END DESCRIPTION:
XS GIS Cut Line= 2
      1981549.73     13910241.08      1982094.76     13909639.04
#Sta/Elev= 30
  4640.3 1521.15  4656.6  1520.9  4723.7 1517.33  4763.9 1514.09  4831.9 1503.06
  4884.5 1498.64    4898 1498.24  4911.4 1496.78  4963.1  1488.9  4999.9 1487.34
  5000.1 1486.84  5003.9 1487.34  5009.9 1488.14  5022.8 1488.23  5030.2 1488.66
    5050 1492.18  5066.6 1494.24  5088.7 1494.05  5107.6 1495.75    5126 1498.37
    5151 1502.95  5167.8 1509.42    5184  1513.8  5236.6 1518.62    5273 1520.97
  5285.2 1521.05  5301.7 1522.58  5358.2 1525.32  5425.5 1526.92  5452.4 1526.84
#Mann= 7 ,-1 , 0
  4640.3      .1       0  4999.9     .05       0  5003.9      .1       0
  5022.8      .1       0  5088.7     .07       0    5151      .1       0
  5301.7     .07       0
#XS Ineff= 2 , 0
                         5068.53         1494.77
Permanent Ineff=
       F       F
Bank Sta=4999.9,5003.9
XS Rating Curve= 0 ,0
Exp/Cntr=0.3,0.1

Chan Stop Cuts=-1
Use User Specified Reach Order=0
Composite Channel Slope=5