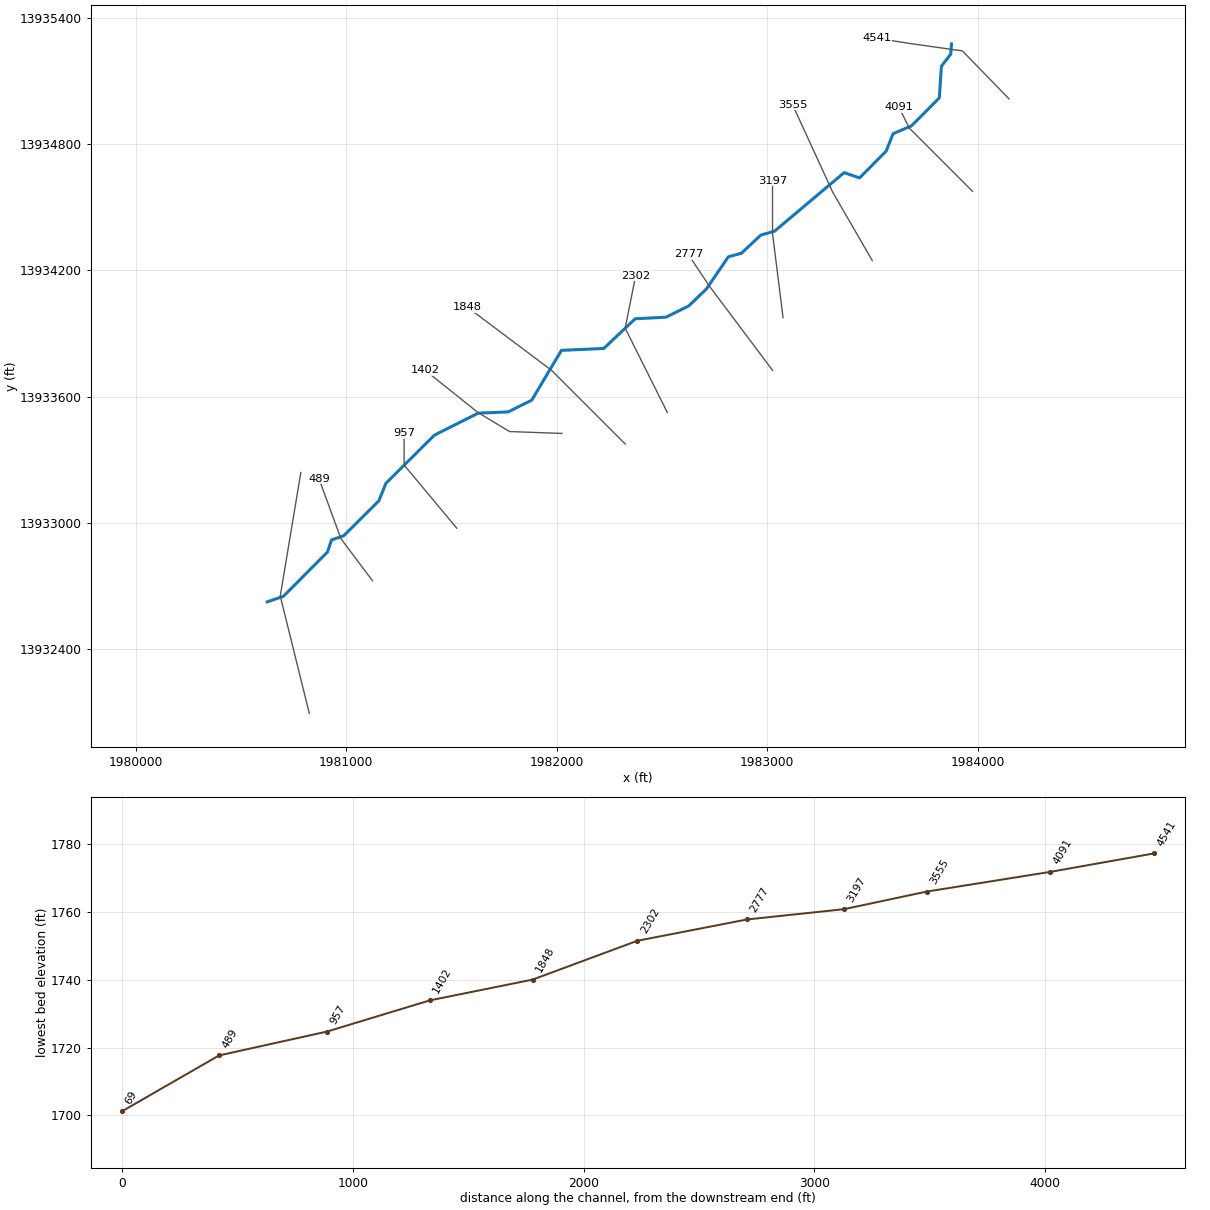
--- Stream0062.prj (project) ---

Proj Title=Stream0062 Base Level Engineering
Current Plan=p01
Default Exp/Contr=0.3,0.1
English Units
Geom File=g01
Flow File=f01
Plan File=p01
BEGIN DESCRIPTION:
Stream0062
END DESCRIPTION:

--- Stream0062.p01 (plan) ---

Plan Title=Multiple Run
Short Identifier=Multiple
Geom File=g01
Flow File=f01
Subcritical Flow
K Sum by GR= 0
Std Step Tol= 0.01
Critical Tol= 0.01
Num of Std Step Trials= 20
Max Error Tol= 0.3
Flow Tol Ratio= 0.001
Split Flow NTrial= 30
Split Flow Tol= 0.02
Split Flow Ratio= 0.02
Log Output Level= 0
Friction Slope Method= 1
Unsteady Friction Slope Method= 2
Unsteady Bridges Friction Slope Method= 1
Parabolic Critical Depth
Global Vel Dist=  1 , 1 , 1
Global Log Level= 0
CheckData=True
Encroach Param= -1, 0, 0, 0
BEGIN DESCRIPTION:
Multiple Run
END DESCRIPTION:

--- Stream0062.f01 (steady flow) ---

Flow Title=Multiple
Number of Profiles=7
Profile Names=10-year,25-year,50-year,1pct_min,100-year,1pct_plu,500-year
River Rch & RM= Stream0062,Reach-1,4541
    1044    1802    2537    1733    3459    6901    6378
River Rch & RM= Stream0062,Reach-1,2777
    1192    2069    2923    2003    3997    7975    7417
Boundary for River Rch & Prof#=Stream0062,Reach-1,1
Up Type=0
Dn Type=3
Dn Slope=0.005
Boundary for River Rch & Prof#=Stream0062,Reach-1,2
Up Type=0
Dn Type=3
Dn Slope=0.005
Boundary for River Rch & Prof#=Stream0062,Reach-1,3
Up Type=0
Dn Type=3
Dn Slope=0.005
Boundary for River Rch & Prof#=Stream0062,Reach-1,4
Up Type=0
Dn Type=3
Dn Slope=0.005
Boundary for River Rch & Prof#=Stream0062,Reach-1,5
Up Type=0
Dn Type=3
Dn Slope=0.005
Boundary for River Rch & Prof#=Stream0062,Reach-1,6
Up Type=0
Dn Type=3
Dn Slope=0.005
Boundary for River Rch & Prof#=Stream0062,Reach-1,7
Up Type=0
Dn Type=3
Dn Slope=0.005

--- Stream0062.g01 (geometry) ---

Geom Title=Existing Conditions

River Reach=Stream0062,Reach-1
Reach XY= 30
      1983875.00     13935275.00      1983871.35     13935226.51
      1983827.14     13935169.12      1983817.19     13935018.81
      1983684.66     13934885.79      1983597.86     13934848.84
      1983564.21     13934765.34      1983438.33     13934638.65
      1983365.00     13934663.76      1983034.68     13934385.78
      1982968.96     13934366.82      1982877.28     13934280.87
      1982815.30     13934264.23      1982711.38     13934111.76
      1982627.31     13934030.82      1982519.07     13933977.25
      1982372.55     13933969.53      1982223.54     13933828.54
      1982022.30     13933819.64      1981881.34     13933583.02
      1981769.07     13933527.25      1981626.56     13933521.24
      1981418.94     13933416.86      1981188.63     13933188.21
      1981155.21     13933104.91      1980987.98     13932938.73
      1980930.62     13932919.38      1980911.27     13932862.02
      1980701.80     13932651.35      1980625.00     13932625.00

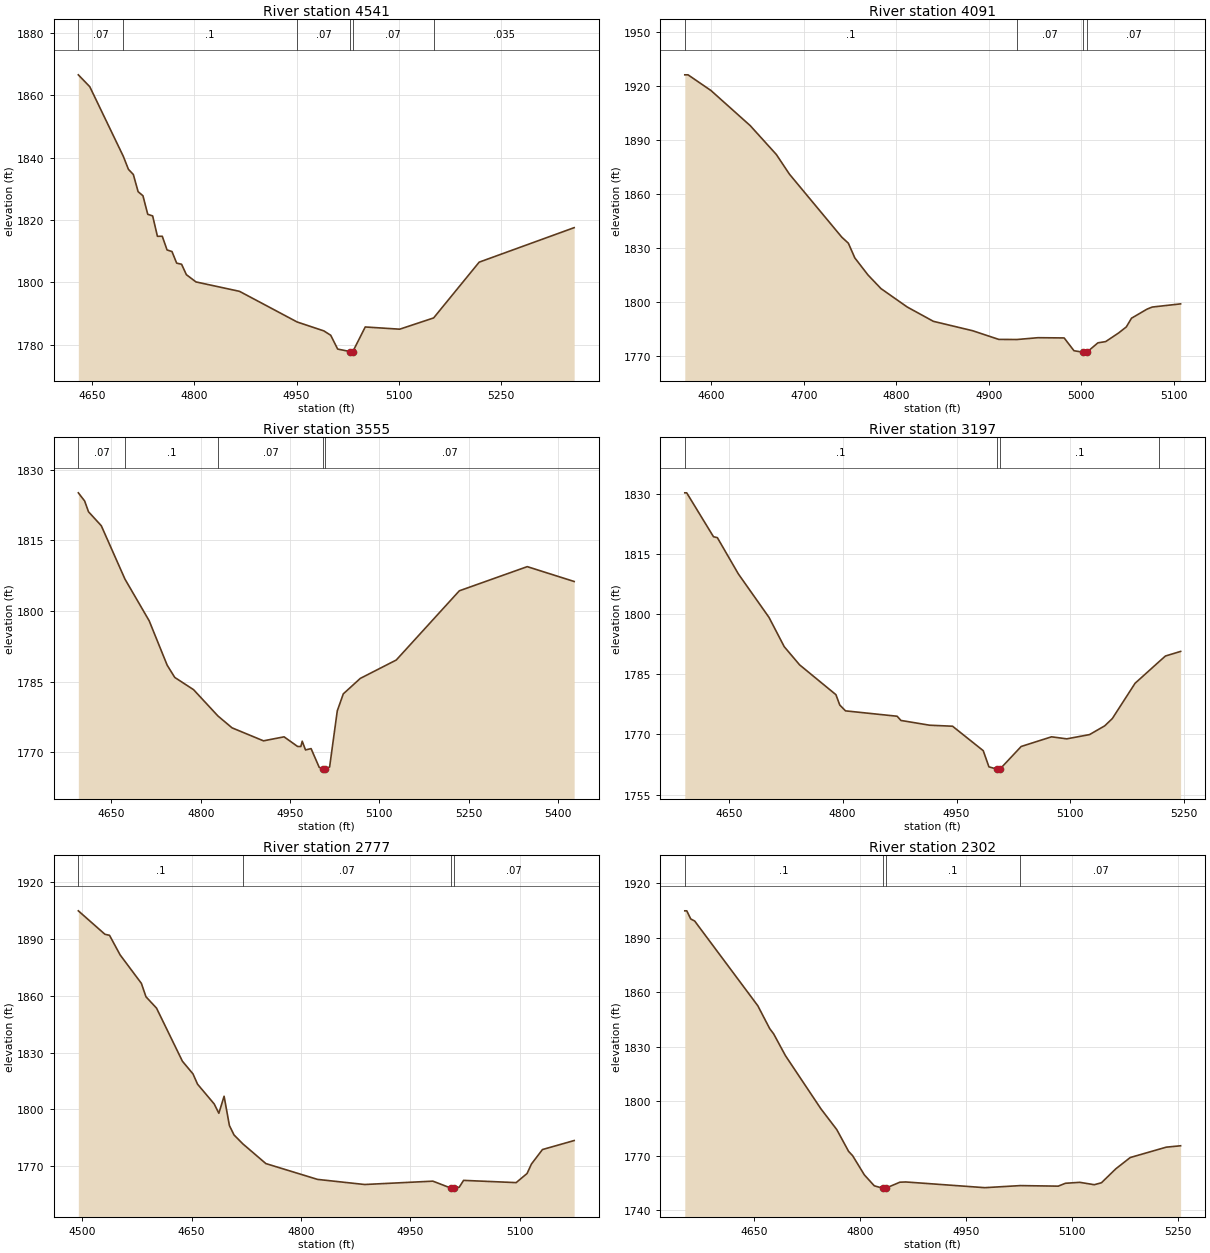
Type RM Length L Ch R = 1,4541,450,450,450
BEGIN DESCRIPTION:
Stream0062 10.0
END DESCRIPTION:
XS GIS Cut Line= 4
      1984148.19     13935014.29      1983926.80     13935242.06
      1983684.14     13935276.12      1983522.32     13935301.67
#Sta/Elev= 30
  4630.3 1866.59  4647.1 1862.77  4696.2 1840.45  4703.7 1836.28  4710.9 1834.61
  4717.9 1829.11  4725.0 1827.79  4732.0 1821.85  4739.2 1821.33  4746.2 1814.79
  4753.3 1814.80  4760.3 1810.41  4767.5 1809.90  4774.4 1806.18  4781.6 1805.82
  4788.6 1802.48  4802.7 1800.15  4866.5 1797.13  4950.9 1787.30  4990.1 1784.44
  5000.1 1783.04  5010.3 1778.61  5028.5 1777.81  5028.8 1777.31  5032.5 1777.81
  5050.7 1785.70  5101.2 1784.99  5150.9 1788.60  5217.6 1806.49  5356.8 1817.56
#Mann=6,-1,0
  4630.3    0.07       0  4696.2     0.1       0  4950.9    0.07       0
  5028.5    0.05       0  5032.5    0.07       0  5150.9   0.035       0
Bank Sta=5028.5,5032.5
Exp/Cntr=0.3,0.1

Type RM Length L Ch R = 1,4091,536,536,536
BEGIN DESCRIPTION:
Stream0062 9.0
END DESCRIPTION:
XS GIS Cut Line= 3
      1983974.98     13934575.02      1983675.00     13934875.00
      1983625.02     13934974.96
#Sta/Elev= 30
  4571.4 1926.46  4574.9 1926.46  4599.7 1917.74  4642.1 1898.25  4670.4 1882.18
  4684.5 1871.29  4741.1 1836.29  4748.2 1832.94  4755.2 1824.76  4769.4 1815.30
  4783.5 1807.70  4811.8 1797.50  4840.1 1789.53  4882.5 1784.31  4910.8 1779.49
  4930.5 1779.42  4953.2 1780.43  4981.5 1780.30  4992.1 1773.20  5002.0 1772.36
  5002.3 1771.86  5006.0 1772.36  5018.0 1777.58  5026.4 1778.27  5040.4 1783.08
  5048.7 1786.43  5054.3 1791.26  5071.1 1796.30  5076.7 1797.46  5107.4 1799.22
#Mann=4,-1,0
  4571.4     0.1       0  4930.5    0.07       0  5002.0    0.05       0
  5006.0    0.07       0
Bank Sta=5002,5006
Exp/Cntr=0.3,0.1

Type RM Length L Ch R = 1,3555,358,358,358
BEGIN DESCRIPTION:
Stream0062 8.0
END DESCRIPTION:
XS GIS Cut Line= 3
      1983498.93     13934245.87      1983311.62     13934569.41
      1983120.06     13934986.58
#Sta/Elev= 30
  4594.3 1825.12  4604.9 1823.39  4611.4 1821.10  4632.9 1818.13  4672.6 1806.81
  4713.3 1797.96  4743.5 1788.54  4756.3 1785.93  4787.9 1783.33  4828.8 1777.75
  4852.5 1775.23  4905.3 1772.47  4939.9 1773.32  4962.7 1771.27  4968.1 1771.27
  4970.4 1772.39  4975.9 1770.54  4985.3 1770.82  4998.9 1766.85  5005.3 1766.54
  5005.6 1766.04  5009.3 1766.54  5016.4 1766.91  5029.3 1778.84  5039.4 1782.44
  5067.9 1785.72  5128.4 1789.63  5234.3 1804.32  5348.4 1809.45  5427.2 1806.30
#Mann=5,-1,0
  4594.3    0.07       0  4672.6     0.1       0  4828.8    0.07       0
  5005.3    0.05       0  5009.3    0.07       0
Bank Sta=5005.3,5009.3
Exp/Cntr=0.3,0.1

Type RM Length L Ch R = 1,3197,420,420,420
BEGIN DESCRIPTION:
Stream0062 7.0
END DESCRIPTION:
XS GIS Cut Line= 3
      1983075.00     13933974.97      1983025.00     13934375.00
      1983025.00     13934624.96
#Sta/Elev= 30
  4592.1 1830.26  4594.6 1830.26  4629.9 1819.31  4635.0 1819.08  4662.7 1810.02
  4703.0 1799.20  4723.1 1791.88  4743.3 1787.36  4791.2 1779.91  4796.2 1777.34
  4803.8 1775.88  4871.8 1774.54  4876.8 1773.49  4914.6 1772.30  4944.8 1772.05
  4985.2 1765.95  4992.7 1761.92  5003.2 1761.35  5003.5 1760.85  5007.2 1761.35
  5035.2 1767.00  5075.2 1769.41  5095.2 1768.90  5125.2 1769.96  5145.2 1772.14
  5155.2 1773.95  5185.2 1782.76  5216.4 1788.08  5225.2 1789.56  5245.2 1790.71
#Mann=4,-1,0
  4592.1     0.1       0  5003.2    0.05       0  5007.2     0.1       0
  5216.4    0.07       0
Bank Sta=5003.2,5007.2
Exp/Cntr=0.3,0.1

Type RM Length L Ch R = 1,2777,475,475,475
BEGIN DESCRIPTION:
Stream0062 6.0
END DESCRIPTION:
XS GIS Cut Line= 3
      1983025.03     13933724.96      1982725.00     13934125.00
      1982625.01     13934274.98
#Sta/Elev= 30
  4494.5 1904.85  4531.0 1892.46  4537.3 1891.91  4551.8 1881.59  4581.0 1866.54
  4587.3 1859.45  4601.8 1853.44  4637.3 1825.40  4651.8 1818.71  4658.1 1813.25
  4681.0 1802.78  4687.3 1797.89  4694.5 1806.89  4701.8 1791.40  4708.1 1786.46
  4720.2 1781.74  4751.8 1771.32  4822.7 1762.96  4887.3 1760.26  4981.0 1762.03
  5006.0 1758.32  5006.3 1757.82  5010.1 1758.32  5017.1 1758.84  5023.1 1762.44
  5095.2 1761.26  5110.2 1766.08  5116.2 1771.09  5131.3 1778.73  5174.8 1783.49
#Mann=4,-1,0
  4494.5     0.1       0  4720.2    0.07       0  5006.0    0.05       0
  5010.1    0.07       0
Bank Sta=5006,5010.1
Exp/Cntr=0.3,0.1

Type RM Length L Ch R = 1,2302,454,454,454
BEGIN DESCRIPTION:
Stream0062 5.0
END DESCRIPTION:
XS GIS Cut Line= 3
      1982524.99     13933525.01      1982325.00     13933925.00
      1982374.99     13934174.95
#Sta/Elev= 30
  4552.3 1904.70  4555.1 1904.70  4560.7 1900.23  4566.3 1899.09  4655.7 1852.46
  4672.5 1839.90  4678.1 1837.00  4694.8 1825.01  4745.1 1795.71  4767.5 1784.31
  4784.3 1772.29  4789.9 1769.98  4806.6 1759.36  4820.6 1753.38  4832.5 1752.04
  4832.8 1751.54  4836.7 1752.04  4856.9 1755.36  4865.3 1755.48  4977.1 1752.34
  5027.4 1753.48  5081.1 1753.18  5091.3 1754.76  5111.7 1755.28  5132.1 1753.97
  5142.3 1755.05  5162.7 1762.74  5183.1 1768.94  5234.1 1774.64  5254.4 1775.40
#Mann=4,-1,0
  4552.3     0.1       0  4832.5    0.05       0  4836.7     0.1       0
  5027.4    0.07       0
Bank Sta=4832.5,4836.7
Exp/Cntr=0.3,0.1

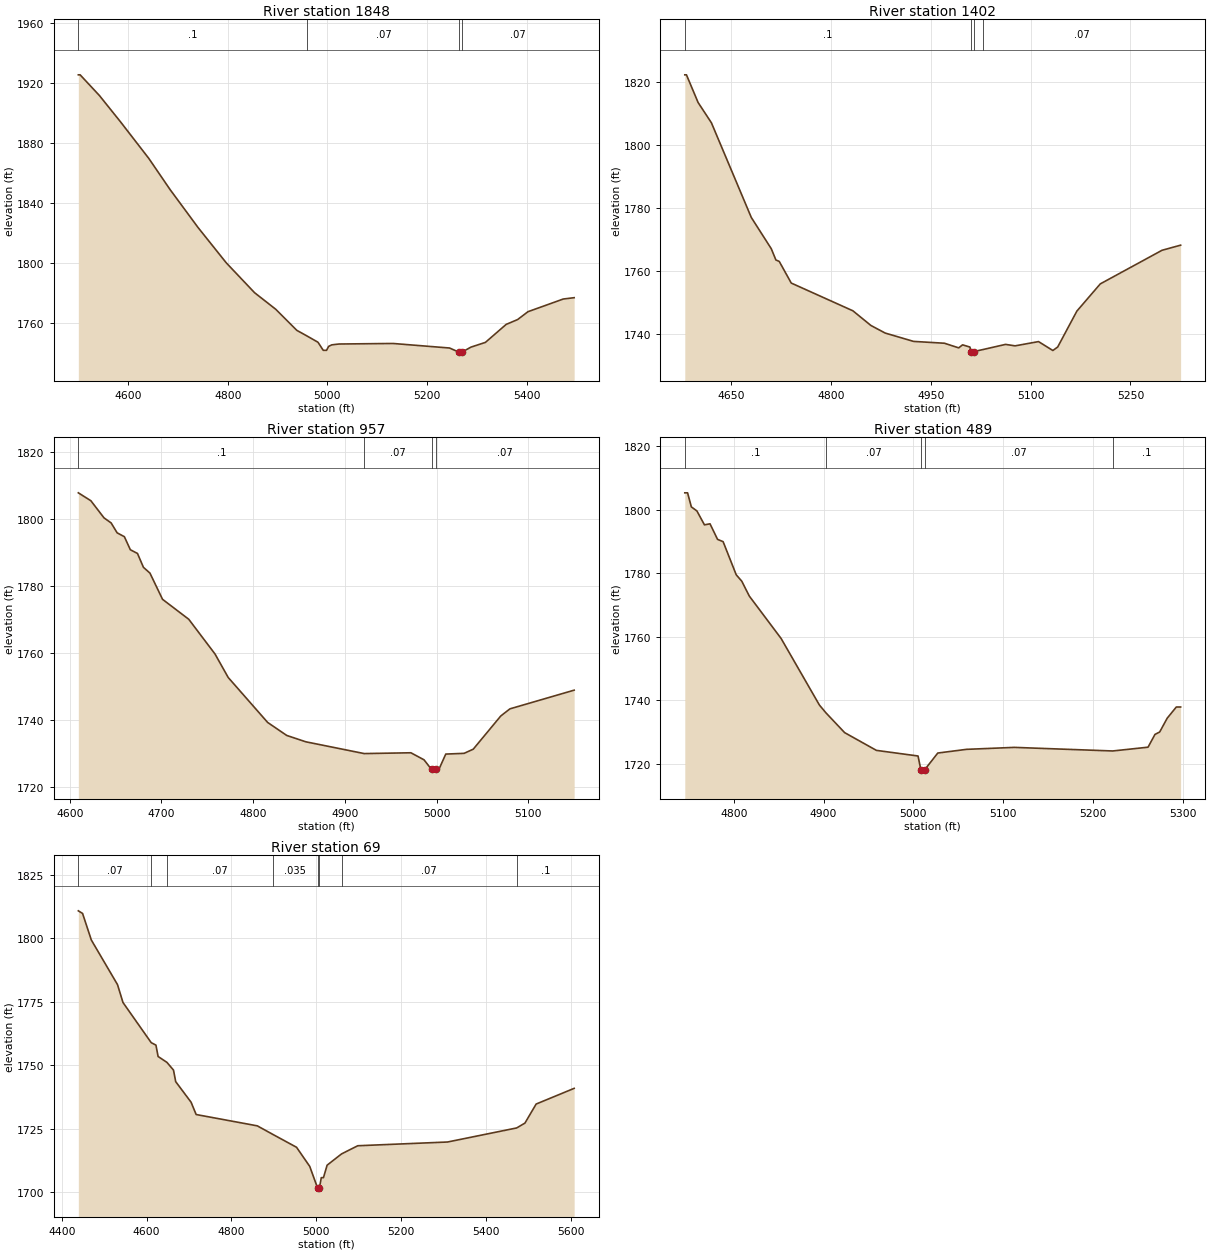
Type RM Length L Ch R = 1,1848,446,446,446
BEGIN DESCRIPTION:
Stream0062 4.0
END DESCRIPTION:
XS GIS Cut Line= 3
      1982325.03     13933374.97      1981975.00     13933725.00
      1981575.01     13934024.99
#Sta/Elev= 30
  4500.2 1925.72  4503.8 1925.72  4542.7 1911.84  4585.1 1894.25  4641.7 1869.93
  4684.1 1849.29  4740.7 1823.76  4797.2 1800.26  4853.8 1780.41  4896.2 1769.38
  4938.6 1755.29  4959.5 1751.44  4981.1 1747.35  4991.7 1741.95  4998.3 1741.95
  5002.5 1744.57  5008.8 1745.59  5023.3 1746.16  5131.7 1746.52  5245.2 1743.49
  5265.0 1740.58  5265.3 1740.08  5269.2 1740.58  5287.9 1744.06  5317.1 1747.24
  5358.8 1759.25  5381.7 1762.46  5402.5 1767.71  5473.3 1776.17  5495.2 1777.06
#Mann=4,-1,0
  4500.2     0.1       0  4959.5    0.07       0  5265.0    0.05       0
  5269.2    0.07       0
Bank Sta=5265,5269.2
Exp/Cntr=0.3,0.1

Type RM Length L Ch R = 1,1402,445,445,445
BEGIN DESCRIPTION:
Stream0062 3.0
END DESCRIPTION:
XS GIS Cut Line= 4
      1982024.97     13933425.00      1981775.73     13933433.98
      1981625.00     13933525.00      1981375.03     13933724.97
#Sta/Elev= 30
  4579.8 1822.25  4582.3 1822.25  4599.8 1813.47  4619.8 1807.04  4679.8 1776.99
  4709.9 1767.05  4716.8 1763.49  4721.8 1763.05  4739.9 1756.17  4832.6 1747.37
  4859.7 1742.71  4881.1 1740.31  4923.8 1737.66  4970.2 1737.08  4991.7 1735.61
  4997.5 1736.57  5008.5 1735.87  5010.4 1734.44  5010.6 1733.94  5014.6 1734.44
  5028.9 1735.11  5062.1 1736.71  5076.5 1736.25  5111.7 1737.60  5133.3 1734.77
  5140.6 1735.90  5169.4 1747.28  5204.6 1755.91  5297.4 1766.57  5325.4 1768.20
#Mann=4,-1,0
  4579.8     0.1       0  5010.4    0.05       0  5014.6     0.1       0
  5028.9    0.07       0
Bank Sta=5010.4,5014.6
Exp/Cntr=0.3,0.1

Type RM Length L Ch R = 1,957,468,468,468
BEGIN DESCRIPTION:
Stream0062 2.0
END DESCRIPTION:
XS GIS Cut Line= 3
      1981525.02     13932974.97      1981275.00     13933275.00
      1981275.00     13933425.05
#Sta/Elev= 30
  4609.4 1807.86  4623.1 1805.49  4637.4 1800.38  4645.2 1798.86  4651.7 1795.91
  4659.6 1794.76  4666.1 1790.87  4673.9 1789.75  4680.4 1785.61  4687.5 1783.88
  4701.2 1776.06  4729.8 1770.10  4758.5 1759.70  4772.8 1752.72  4815.8 1739.29
  4836.6 1735.41  4857.4 1733.51  4921.1 1729.99  4972.0 1730.23  4986.3 1728.13
  4994.5 1725.25  4994.8 1724.75  4998.9 1725.25  5002.5 1725.25  5010.0 1729.84
  5030.0 1730.06  5040.0 1731.31  5070.0 1741.22  5080.0 1743.35  5150.0 1748.93
#Mann=4,-1,0
  4609.4     0.1       0  4921.1    0.07       0  4994.5    0.05       0
  4998.9    0.07       0
Bank Sta=4994.5,4998.9
Exp/Cntr=0.3,0.1

Type RM Length L Ch R = 1,489,420,420,420
BEGIN DESCRIPTION:
Stream0062 1.0
END DESCRIPTION:
XS GIS Cut Line= 3
      1981125.00     13932725.00      1980975.00     13932925.00
      1980870.97     13933209.05
#Sta/Elev= 30
  4745.4 1805.25  4748.5 1805.25  4752.7 1800.83  4758.9 1799.54  4767.3 1795.18
  4773.5 1795.50  4781.9 1790.61  4788.1 1789.89  4802.7 1779.47  4808.9 1777.45
  4817.3 1772.76  4852.7 1759.44  4895.4 1738.49  4902.6 1736.06  4923.5 1729.81
  4958.9 1724.23  5005.3 1722.46  5008.4 1718.20  5008.8 1717.70  5012.9 1718.20
  5027.3 1723.39  5059.3 1724.55  5112.5 1725.17  5222.2 1724.04  5261.6 1725.23
  5269.3 1729.24  5274.6 1730.02  5282.9 1734.33  5293.1 1737.87  5297.9 1737.87
#Mann=5,-1,0
  4745.4     0.1       0  4902.6    0.07       0  5008.4    0.05       0
  5012.9    0.07       0  5222.2     0.1       0
Bank Sta=5008.4,5012.9
Exp/Cntr=0.3,0.1

Type RM Length L Ch R = 1,69,0,0,0
BEGIN DESCRIPTION:
Stream00620 0.0
END DESCRIPTION:
XS GIS Cut Line= 3
      1980824.65     13932095.32      1980686.76     13932653.02
      1980784.56     13933239.53
#Sta/Elev= 30
  4438.9 1810.88  4448.9 1809.85  4469.5 1799.40  4531.3 1781.80  4544.2 1774.76
  4610.7 1758.95  4621.9 1757.97  4627.0 1753.49  4647.8 1751.18  4663.3 1748.13
  4668.5 1743.58  4704.8 1735.47  4716.7 1730.63  4860.9 1726.17  4897.0 1722.85
  4953.4 1717.73  4984.5 1710.21  5002.9 1701.74  5003.2 1701.24  5007.4 1701.74
  5011.8 1705.76  5016.9 1705.76  5025.5 1710.67  5059.5 1715.11  5097.7 1718.33
  5309.4 1719.80  5472.4 1725.34  5491.9 1727.25  5518.4 1734.76  5608.0 1740.94
#Mann=8,-1,0
  4438.9    0.07       0  4610.7     0.1       0  4647.8    0.07       0
  4897.0   0.035       0  5002.9   0.035       0  5007.4   0.035       0
  5059.5    0.07       0  5472.4     0.1       0
Bank Sta=5002.9,5007.4
Exp/Cntr=0.3,0.1

Chan Stop Cuts=-1