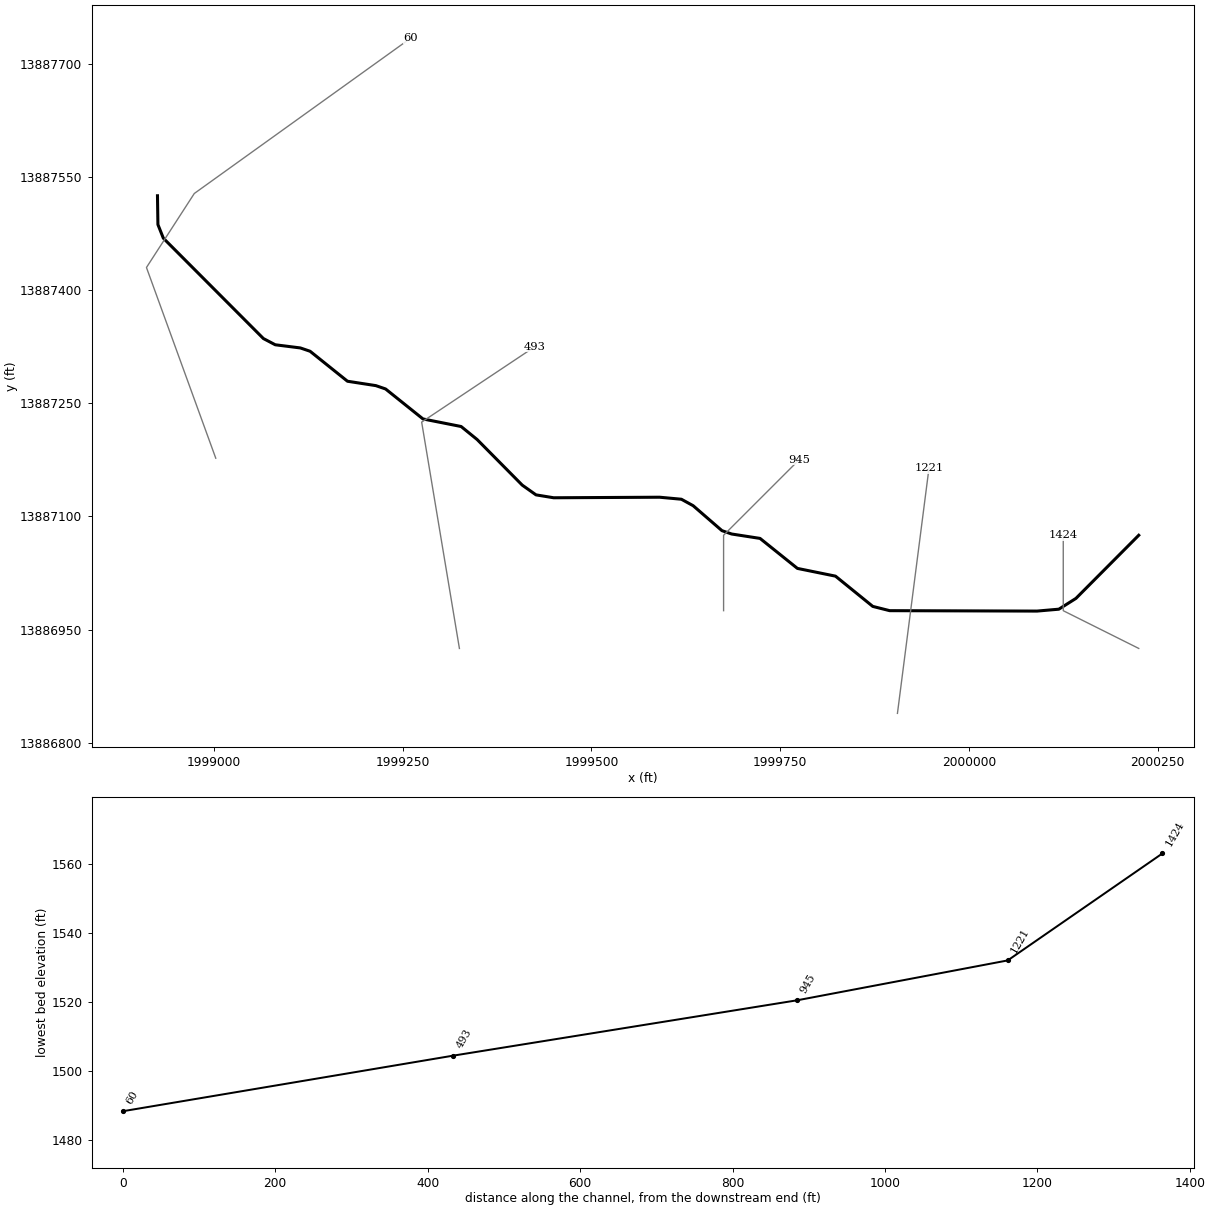
--- Stream0063.prj (project) ---

Proj Title=Stream0063 Base Level Engineering
Current Plan=p01
Default Exp/Contr=0.3,0.1
English Units
Geom File=g01
Flow File=f01
Plan File=p01
Y Axis Title=Elevation
X Axis Title(PF)=Main Channel Distance
X Axis Title(XS)=Station
BEGIN DESCRIPTION:
Stream0063
END DESCRIPTION:
DSS Export Rating Curves= 0
DSS Export Rating Curve Sorted= 0
DSS Export Volume Flow Curves= 0
DXF OffsetX= 0
DXF OffsetY= 0
DXF ScaleX= 1
DXF ScaleY= 10

--- Stream0063.p01 (plan) ---

Plan Title=Multiple Run
Short Identifier=Multiple
Geom File=g01
Flow File=f01
Subcritical Flow
K Sum by GR= 0
Std Step Tol= 0.01
Critical Tol= 0.01
Num of Std Step Trials= 20
Max Error Tol= 0.3
Flow Tol Ratio= 0.001
Split Flow NTrial= 30
Split Flow Tol= 0.02
Split Flow Ratio= 0.02
Log Output Level= 0
Friction Slope Method= 1
Unsteady Friction Slope Method= 2
Unsteady Bridges Friction Slope Method= 1
Parabolic Critical Depth
Global Vel Dist=  1 , 1 , 1
Global Log Level= 0
CheckData=True
Encroach Param= -1, 0, 0, 0
BEGIN DESCRIPTION:
Multiple Run
END DESCRIPTION:

--- Stream0063.f01 (steady flow) ---

Flow Title=Multiple
Program Version=4.10
Number of Profiles= 7
Profile Names=10-year,25-year,50-year,1pct_min,100-year,1pct_plu,500-year
River Rch & RM=Stream0063,Reach-1         ,1424
     279     438     579     374     746    1488    1218
Boundary for River Rch & Prof#=Stream0063,Reach-1         , 1
Up Type= 0
Dn Type= 3
Dn Slope=0.005
Boundary for River Rch & Prof#=Stream0063,Reach-1         , 2
Up Type= 0
Dn Type= 3
Dn Slope=0.005
Boundary for River Rch & Prof#=Stream0063,Reach-1         , 3
Up Type= 0
Dn Type= 3
Dn Slope=0.005
Boundary for River Rch & Prof#=Stream0063,Reach-1         , 4
Up Type= 0
Dn Type= 3
Dn Slope=0.005
Boundary for River Rch & Prof#=Stream0063,Reach-1         , 5
Up Type= 0
Dn Type= 3
Dn Slope=0.005
Boundary for River Rch & Prof#=Stream0063,Reach-1         , 6
Up Type= 0
Dn Type= 3
Dn Slope=0.005
Boundary for River Rch & Prof#=Stream0063,Reach-1         , 7
Up Type= 0
Dn Type= 3
Dn Slope=0.005
DSS Import GetInterval= 0
DSS Import GetPeak= 0
DSS Import FillOption= 0

--- Stream0063.g01 (geometry) ---

Geom Title=Existing Conditions

River Reach=Stream0063,Reach-1
Reach XY= 30
      2000225.00     13887075.00      2000141.81     13886991.33
      2000119.16     13886977.02      2000090.20     13886974.51
      1999895.03     13886975.06      1999872.65     13886980.71
      1999823.26     13887020.81      1999772.80     13887031.08
      1999723.28     13887070.84      1999685.69     13887076.67
      1999672.82     13887081.12      1999634.67     13887114.20
      1999619.07     13887122.76      1999590.18     13887125.43
      1999449.88     13887124.71      1999426.47     13887128.55
      1999408.25     13887141.46      1999348.44     13887201.94
      1999327.29     13887219.15      1999276.74     13887229.19
      1999227.20     13887268.92      1999214.31     13887273.35
      1999176.72     13887279.16      1999127.19     13887318.90
      1999114.30     13887323.30      1999081.03     13887327.50
      1999065.32     13887335.76      1998932.76     13887468.79
      1998925.59     13887486.84      1998925.00     13887525.00

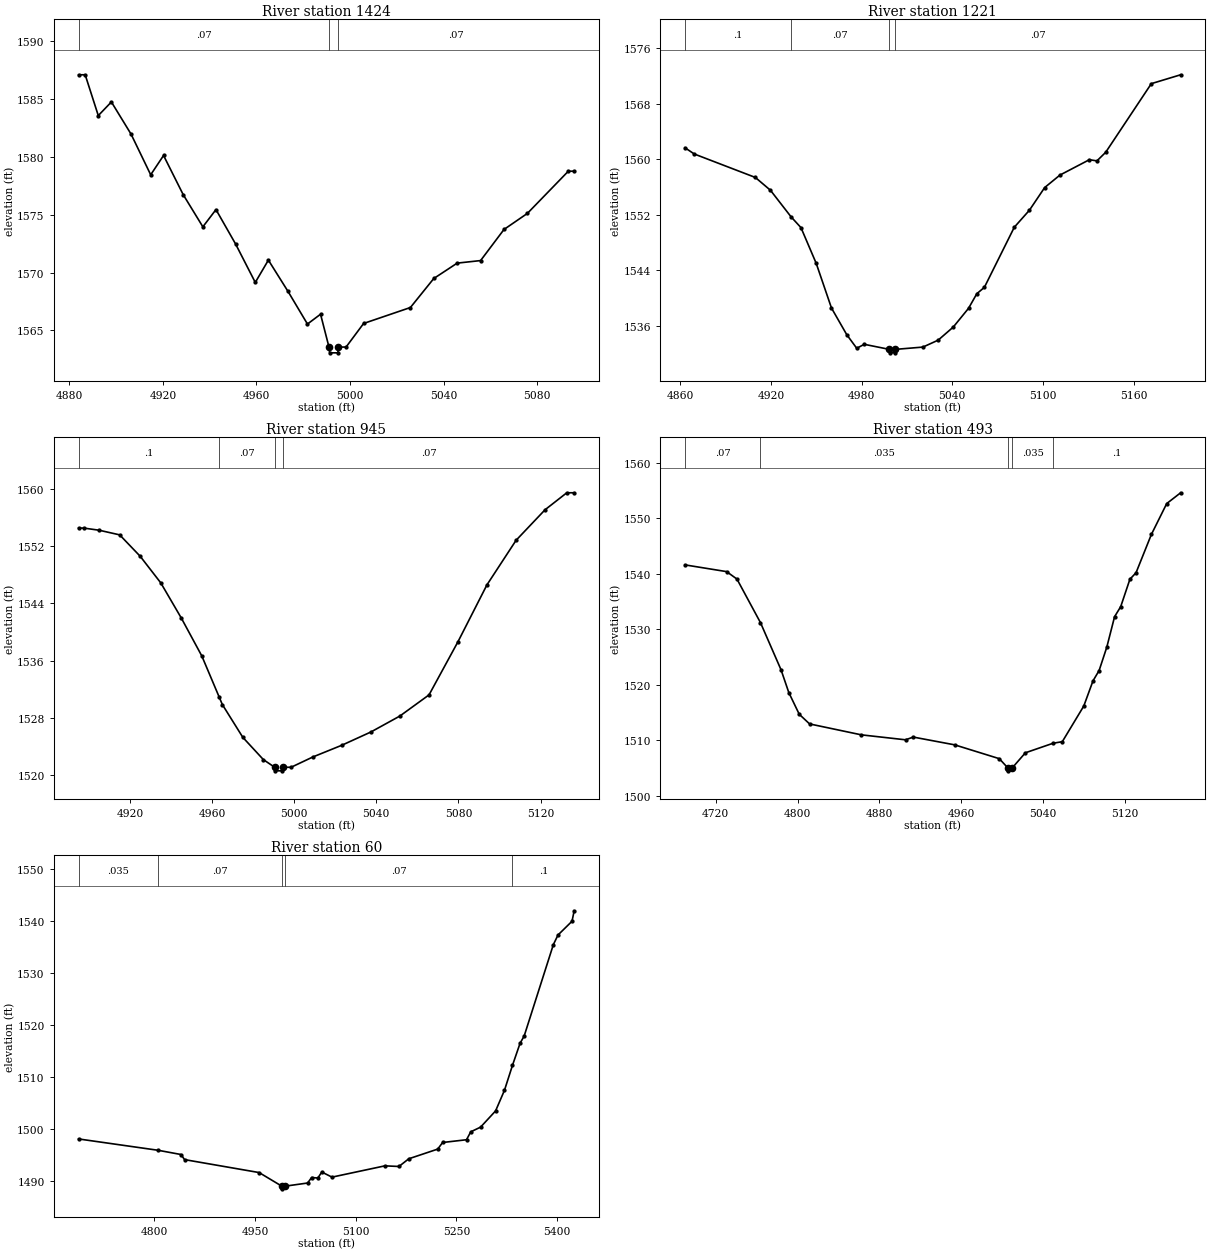
Type RM Length L Ch R = 1,1424,203,203,203
BEGIN DESCRIPTION:
Stream0063 3.0
END DESCRIPTION:
XS GIS Cut Line= 3
      2000225.01     13886925.00      2000125.00     13886975.00
      2000125.00     13887074.99
#Sta/Elev= 30
  4884.0 1587.11  4886.8 1587.11  4892.4 1583.58  4898.0 1584.76  4906.4 1581.98
  4914.8 1578.46  4920.3 1580.13  4928.7 1576.74  4937.1 1573.96  4942.7 1575.45
  4951.1 1572.47  4959.5 1569.15  4965.1 1571.08  4973.5 1568.37  4981.8 1565.55
  4987.4 1566.40  4991.0 1563.56  4991.3 1563.06  4994.8 1563.06  4995.0 1563.56
  4998.3 1563.56  5005.8 1565.60  5025.8 1566.98  5035.8 1569.49  5045.8 1570.82
  5055.8 1571.04  5065.8 1573.73  5075.8 1575.12  5093.3 1578.77  5095.8 1578.77
#Mann=3,-1,0
  4884.0    0.07       0  4991.0    0.05       0  4995.0    0.07       0
Bank Sta=4991,4995
Exp/Cntr=0.3,0.1

Type RM Length L Ch R = 1,1221,276,276,276
BEGIN DESCRIPTION:
Mapping XS 6054a05f
END DESCRIPTION:
XS GIS Cut Line= 2
      1999905.32     13886838.92      1999947.15     13887164.24
#Sta/Elev= 30
  4863.2 1561.66  4869.3 1560.77  4909.7 1557.39  4919.7 1555.54  4933.3 1551.72
  4939.9 1550.15  4950.0 1544.99  4960.1 1538.55  4970.2 1534.71  4976.8 1532.75
  4981.8 1533.32  4998.4 1532.59  4998.7 1532.09  5002.2 1532.09  5002.4 1532.59
  5020.6 1532.92  5030.7 1533.92  5040.7 1535.81  5050.8 1538.51  5056.3 1540.62
  5061.3 1541.54  5081.1 1550.21  5091.1 1552.66  5101.2 1555.93  5111.3 1557.73
  5130.8 1559.95  5135.8 1559.78  5141.6 1561.02  5171.8 1570.92  5191.2 1572.20
#Mann=4,-1,0
  4863.2     0.1       0  4933.3    0.07       0  4998.4    0.05       0
  5002.4    0.07       0
Bank Sta=4998.4,5002.4
Exp/Cntr=0.3,0.1

Type RM Length L Ch R = 1,945,452,452,452
BEGIN DESCRIPTION:
Stream0063 2.0
END DESCRIPTION:
XS GIS Cut Line= 3
      1999675.00     13886975.05      1999675.00     13887075.00
      1999775.02     13887175.02
#Sta/Elev= 29
  4895.0 1554.53  4897.5 1554.53  4905.0 1554.23  4915.0 1553.58  4925.0 1550.58
  4935.0 1546.87  4945.0 1541.95  4955.0 1536.64  4963.4 1530.93  4965.0 1529.84
  4975.0 1525.24  4985.0 1522.13  4990.5 1521.06  4990.7 1520.56  4994.2 1520.56
  4994.5 1521.06  4995.0 1521.06  4998.5 1521.06  5009.1 1522.50  5023.2 1524.14
  5037.4 1526.00  5051.5 1528.23  5065.7 1531.19  5079.8 1538.63  5093.9 1546.58
  5108.1 1552.82  5122.2 1557.09  5132.8 1559.47  5136.4 1559.47
#Mann=4,-1,0
  4895.0     0.1       0  4963.4    0.07       0  4990.5    0.05       0
  4994.5    0.07       0
Bank Sta=4990.5,4994.5
Exp/Cntr=0.3,0.1

Type RM Length L Ch R = 1,493,433,433,433
BEGIN DESCRIPTION:
Stream0063 1.0
END DESCRIPTION:
XS GIS Cut Line= 3
      1999325.01     13886924.96      1999275.00     13887225.00
      1999425.04     13887325.02
#Sta/Elev= 30
  4690.1 1541.60  4730.7 1540.39  4740.8 1539.05  4763.8 1531.20  4783.9 1522.71
  4791.5 1518.61  4801.7 1514.70  4811.8 1512.96  4862.5 1510.99  4905.6 1510.10
  4913.2 1510.59  4953.7 1509.19  4997.3 1506.70  5005.8 1505.01  5006.1 1504.51
  5009.8 1505.01  5022.8 1507.76  5049.9 1509.48  5058.9 1509.76  5079.9 1516.18
  5088.9 1520.71  5094.9 1522.58  5102.4 1526.78  5110.0 1532.27  5116.0 1534.08
  5125.0 1539.02  5131.0 1540.19  5146.0 1547.09  5161.0 1552.65  5174.6 1554.59
#Mann=5,-1,0
  4690.1    0.07       0  4763.8   0.035       0  5005.8   0.035       0
  5009.8   0.035       0  5049.9     0.1       0
Bank Sta=5005.8,5009.8
Exp/Cntr=0.3,0.1

Type RM Length L Ch R = 1,60,0,0,0
BEGIN DESCRIPTION:
Stream0063 0.0
END DESCRIPTION:
XS GIS Cut Line= 4
      1999002.22     13887177.14      1998910.40     13887429.92
      1998973.77     13887528.01      1999260.15     13887733.68
#Sta/Elev= 30
  4687.1 1498.03  4805.7 1495.85  4839.6 1495.04  4844.9 1494.06  4956.0 1491.57
  4990.0 1488.94  4990.3 1488.44  4994.0 1488.94  5028.3 1489.56  5034.2 1490.62
  5043.5 1490.52  5049.4 1491.67  5064.6 1490.69  5143.4 1492.86  5164.3 1492.74
  5179.0 1494.22  5222.1 1496.08  5229.4 1497.35  5265.0 1497.88  5271.3 1499.40
  5285.9 1500.30  5308.3 1503.42  5321.5 1507.37  5333.5 1512.19  5344.8 1516.43
  5350.9 1517.82  5394.4 1535.40  5401.3 1537.24  5422.2 1539.89  5425.4 1541.90
#Mann=5,-1,0
  4687.1   0.035       0  4805.7    0.07       0  4990.0    0.05       0
  4994.0    0.07       0  5333.5     0.1       0
Bank Sta=4990,4994
Exp/Cntr=0.3,0.1

Chan Stop Cuts=-1