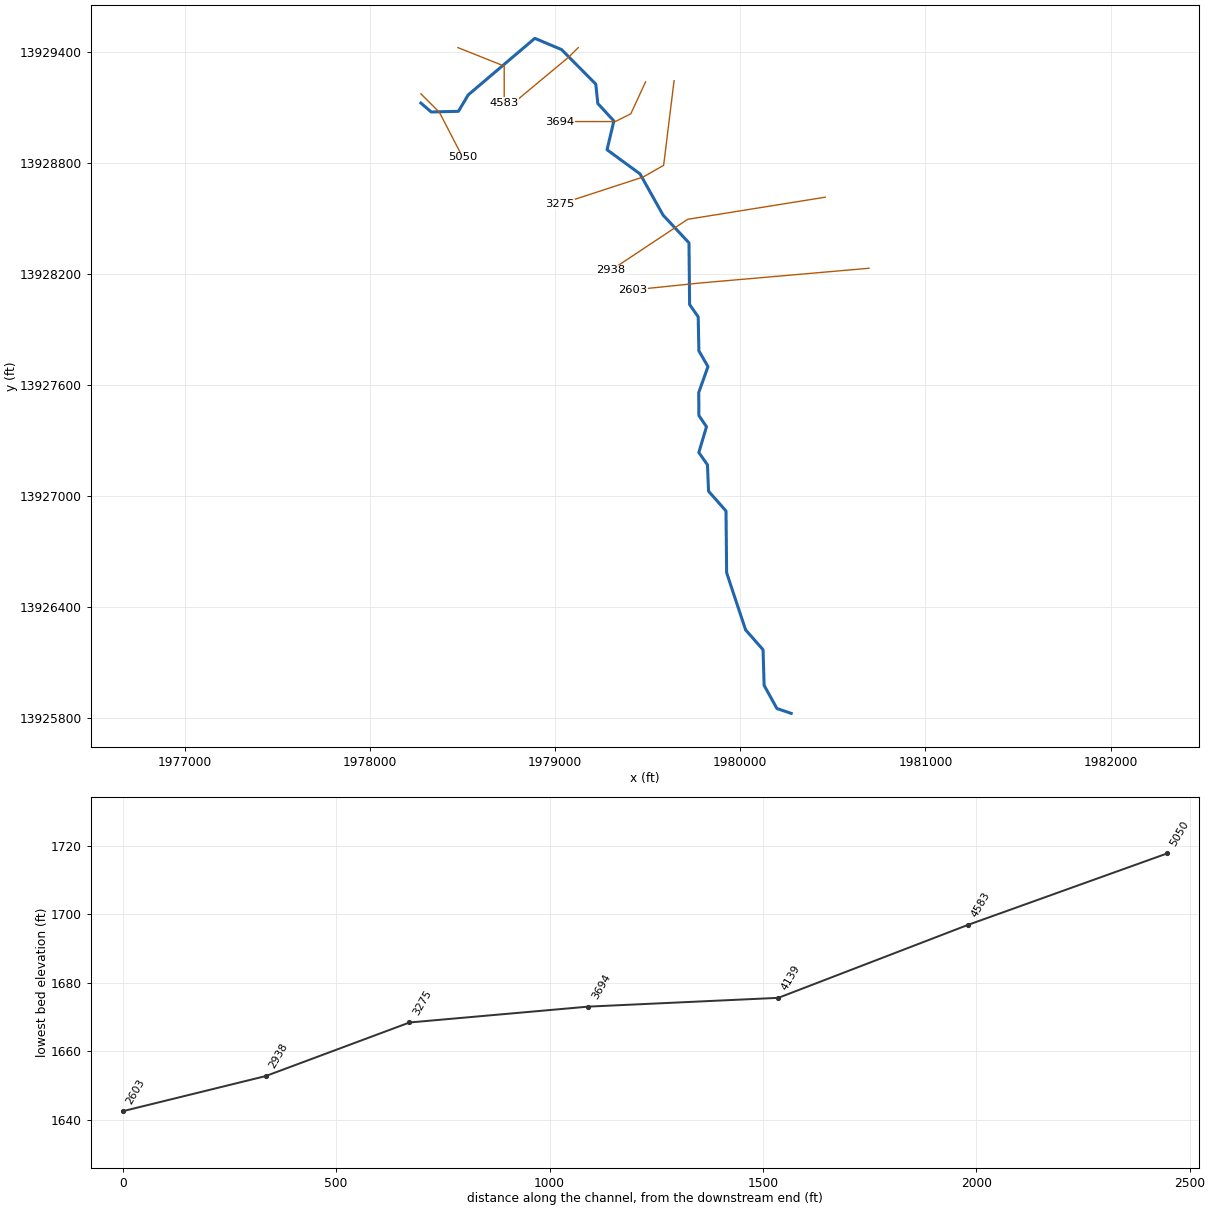
--- Stream0065.prj (project) ---

Proj Title=Stream0065 Base Level Engineering
Current Plan=p01
Default Exp/Contr=0.3,0.1
English Units
Geom File=g01
Flow File=f01
Plan File=p01
BEGIN DESCRIPTION:
Stream0065
END DESCRIPTION:

--- Stream0065.p01 (plan) ---

Plan Title=Multiple Run
Short Identifier=Multiple
Geom File=g01
Flow File=f01
Subcritical Flow
K Sum by GR= 0
Std Step Tol= 0.01
Critical Tol= 0.01
Num of Std Step Trials= 20
Max Error Tol= 0.3
Flow Tol Ratio= 0.001
Split Flow NTrial= 30
Split Flow Tol= 0.02
Split Flow Ratio= 0.02
Log Output Level= 0
Friction Slope Method= 1
Unsteady Friction Slope Method= 2
Unsteady Bridges Friction Slope Method= 1
Parabolic Critical Depth
Global Vel Dist=  1 , 1 , 1
Global Log Level= 0
CheckData=True
Encroach Param= -1, 0, 0, 0
BEGIN DESCRIPTION:
Multiple Run
END DESCRIPTION:

--- Stream0065.f01 (steady flow) ---

Flow Title=Multiple
Number of Profiles=7
Profile Names=10-year,25-year,50-year,1pct_min,100-year,1pct_plu,500-year
River Rch & RM= Stream0065,Reach-1,5050
     700    1178    1632    1098    2192    4373    3918
Boundary for River Rch & Prof#=Stream0065,Reach-1,1
Up Type=0
Dn Type=3
Dn Slope=0.005
Boundary for River Rch & Prof#=Stream0065,Reach-1,2
Up Type=0
Dn Type=3
Dn Slope=0.005
Boundary for River Rch & Prof#=Stream0065,Reach-1,3
Up Type=0
Dn Type=3
Dn Slope=0.005
Boundary for River Rch & Prof#=Stream0065,Reach-1,4
Up Type=0
Dn Type=3
Dn Slope=0.005
Boundary for River Rch & Prof#=Stream0065,Reach-1,5
Up Type=0
Dn Type=3
Dn Slope=0.005
Boundary for River Rch & Prof#=Stream0065,Reach-1,6
Up Type=0
Dn Type=3
Dn Slope=0.005
Boundary for River Rch & Prof#=Stream0065,Reach-1,7
Up Type=0
Dn Type=3
Dn Slope=0.005

--- Stream0065.g01 (geometry) ---

Geom Title=Existing Conditions

River Reach=Stream0065,Reach-1
Reach XY= 30
      1978275.00     13929125.00      1978330.79     13929076.88
      1978477.68     13929080.39      1978530.64     13929169.35
      1978890.34     13929475.05      1979034.68     13929414.24
      1979219.48     13929227.43      1979230.55     13929122.57
      1979317.19     13929028.41      1979280.39     13928872.56
      1979458.50     13928742.05      1979583.16     13928518.95
      1979722.94     13928369.15      1979726.22     13928035.50
      1979772.74     13927969.06      1979776.22     13927785.50
      1979825.40     13927700.00      1979775.51     13927559.78
      1979776.37     13927435.44      1979817.44     13927375.00
      1979776.11     13927235.55      1979822.73     13927169.06
      1979828.56     13927026.47      1979922.93     13926919.14
      1979926.22     13926585.50      1980028.62     13926276.50
      1980122.93     13926169.14      1980128.75     13925976.55
      1980197.72     13925851.15      1980275.00     13925825.00

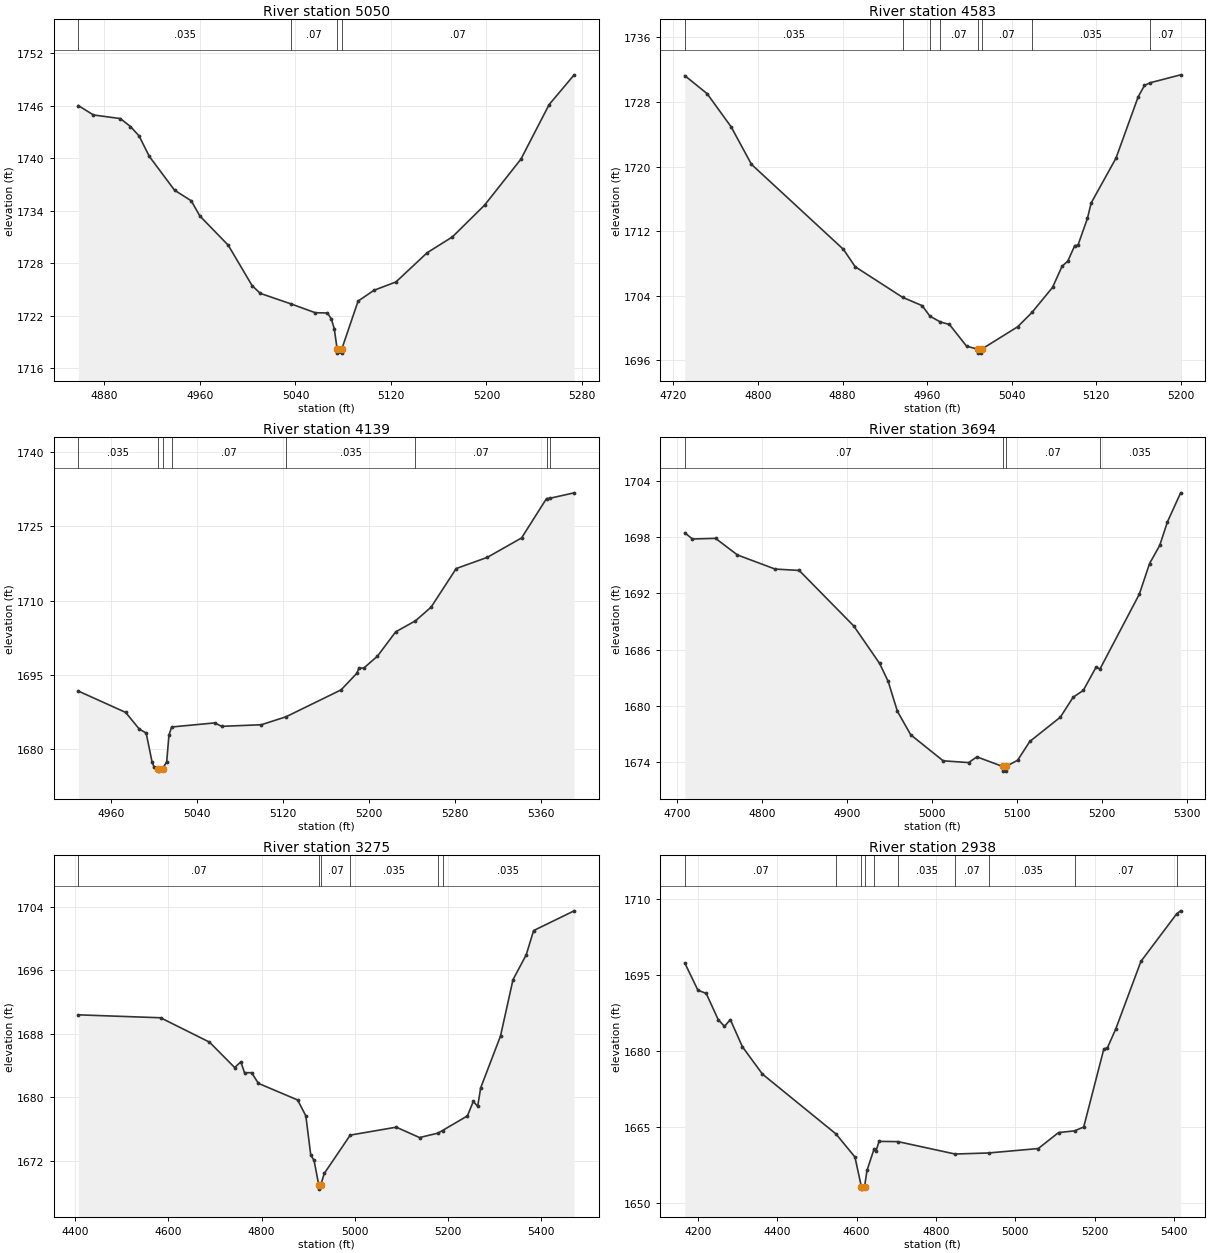
Type RM Length L Ch R = 1,5050,467,467,467
BEGIN DESCRIPTION:
Stream0065 5.0
END DESCRIPTION:
XS GIS Cut Line= 3
      1978275.02     13929174.98      1978375.00     13929075.00
      1978500.91     13928831.63
#Sta/Elev= 30
  4858.1 1745.99  4870.8 1744.92  4893.3 1744.51  4901.8 1743.60  4909.0 1742.53
  4917.5 1740.21  4938.7 1736.34  4952.7 1735.13  4959.9 1733.40  4983.7 1730.06
  5003.7 1725.45  5010.5 1724.57  5036.4 1723.36  5056.6 1722.36  5066.8 1722.33
  5070.1 1721.64  5072.5 1720.54  5074.9 1718.25  5075.1 1717.75  5078.6 1717.75
  5078.9 1718.25  5092.5 1723.69  5105.8 1724.92  5124.2 1725.87  5150.4 1729.21
  5171.5 1731.01  5198.5 1734.64  5228.9 1739.88  5252.5 1746.10  5273.5 1749.50
#Mann=4,-1,0
  4858.1   0.035       0  5036.4    0.07       0  5074.9   0.035       0
  5078.9    0.07       0
Bank Sta=5074.9,5078.9
Exp/Cntr=0.3,0.1

Type RM Length L Ch R = 1,4583,444,444,444
BEGIN DESCRIPTION:
Stream0065 4.0
END DESCRIPTION:
XS GIS Cut Line= 3
      1978474.95     13929425.02      1978725.00     13929325.00
      1978725.00     13929125.01
#Sta/Elev= 30
  4730.7 1731.27  4751.8 1729.04  4774.5 1724.94  4793.8 1720.28  4880.9 1709.74
  4892.0 1707.59  4936.9 1703.80  4955.4 1702.77  4962.7 1701.47  4972.6 1700.75
  4981.2 1700.44  4997.4 1697.75  5007.8 1697.39  5008.0 1696.89  5011.5 1696.89
  5011.8 1697.39  5045.8 1700.16  5059.3 1701.93  5078.8 1705.04  5087.8 1707.66
  5093.2 1708.28  5099.8 1710.22  5102.8 1710.25  5111.8 1713.59  5115.3 1715.49
  5138.8 1721.04  5159.8 1728.64  5165.8 1730.06  5171.2 1730.39  5200.0 1731.37
#Mann=8,-1,0
  4730.7   0.035       0  4936.9    0.07       0  4962.7   0.035       0
  4972.6    0.07       0  5007.8    0.05       0  5011.8    0.07       0
  5059.3   0.035       0  5171.2    0.07       0
Bank Sta=5007.8,5011.8
Exp/Cntr=0.3,0.1

Type RM Length L Ch R = 1,4139,445,445,445
BEGIN DESCRIPTION:
Stream0065 3.0
END DESCRIPTION:
XS GIS Cut Line= 4
      1979125.00     13929425.00      1979125.00     13929425.00
      1979075.00     13929375.00      1978775.02     13929125.02
#Sta/Elev= 30
  4929.5 1691.77  4973.5 1687.47  4986.2 1684.11  4992.6 1683.31  4998.0 1677.57
  4999.9 1676.47  5004.0 1676.13  5004.2 1675.63  5008.0 1676.13  5011.7 1677.54
  5013.8 1682.90  5016.3 1684.53  5056.4 1685.35  5062.8 1684.66  5099.7 1684.98
  5122.6 1686.58  5173.9 1692.01  5188.5 1695.34  5190.6 1696.41  5194.9 1696.38
  5207.7 1698.80  5224.7 1703.71  5243.1 1705.93  5257.6 1708.68  5281.0 1716.47
  5309.9 1718.72  5341.8 1722.64  5365.0 1730.58  5368.1 1730.63  5390.7 1731.73
#Mann=8,-1,0
  4929.5   0.035       0  5004.0   0.035       0  5008.0   0.035       0
  5016.3    0.07       0  5122.6   0.035       0  5243.1    0.07       0
  5365.0   0.035       0  5368.1    0.07       0
Bank Sta=5004,5008
Exp/Cntr=0.3,0.1

Type RM Length L Ch R = 1,3694,419,419,419
BEGIN DESCRIPTION:
Stream0065 2.0
END DESCRIPTION:
XS GIS Cut Line= 4
      1979488.33     13929239.55      1979408.69     13929066.85
      1979325.00     13929025.00      1979024.95     13929025.00
#Sta/Elev= 30
  4708.9 1698.46  4717.9 1697.80  4745.1 1697.87  4770.9 1696.10  4815.2 1694.60
  4843.6 1694.45  4907.8 1688.54  4938.3 1684.54  4948.4 1682.62  4959.2 1679.45
  4974.9 1676.94  5013.1 1674.17  5043.1 1673.98  5052.8 1674.59  5083.1 1673.57
  5083.3 1673.07  5086.8 1673.07  5087.1 1673.57  5100.8 1674.23  5115.1 1676.23
  5151.1 1678.82  5166.1 1680.94  5178.1 1681.67  5193.1 1684.14  5197.8 1683.96
  5244.1 1691.93  5256.1 1695.18  5268.1 1697.12  5277.1 1699.61  5292.7 1702.72
#Mann=4,-1,0
  4708.9    0.07       0  5083.1    0.05       0  5087.1    0.07       0
  5197.8   0.035       0
Bank Sta=5083.1,5087.1
Exp/Cntr=0.3,0.1

Type RM Length L Ch R = 1,3275,337,337,337
BEGIN DESCRIPTION:
Stream0065 1.0
END DESCRIPTION:
XS GIS Cut Line= 4
      1979642.42     13929246.04      1979586.00     13928788.18
      1979475.00     13928725.00      1979023.89     13928577.67
#Sta/Elev= 30
  4406.8 1690.41  4583.2 1690.04  4688.1 1686.97  4742.1 1683.77  4755.4 1684.48
  4763.3 1683.11  4778.4 1683.12  4793.1 1681.77  4877.2 1679.68  4894.8 1677.68
  4905.4 1672.73  4912.5 1672.06  4922.6 1668.94  4922.8 1668.44  4926.6 1668.94
  4934.4 1670.42  4990.1 1675.25  5088.8 1676.25  5138.7 1674.94  5178.3 1675.50
  5188.0 1675.83  5241.4 1677.67  5254.0 1679.49  5263.5 1678.87  5269.8 1681.19
  5312.4 1687.74  5339.2 1694.84  5367.6 1697.98  5383.4 1701.03  5470.4 1703.52
#Mann=6,-1,0
  4406.8    0.07       0  4922.6   0.035       0  4926.6    0.07       0
  4990.1   0.035       0  5178.3    0.07       0  5188.0   0.035       0
Bank Sta=4922.6,4926.6
Exp/Cntr=0.3,0.1

Type RM Length L Ch R = 1,2938,335,335,335
BEGIN DESCRIPTION:
Stream0065 T
END DESCRIPTION:
XS GIS Cut Line= 3
      1980458.26     13928615.95      1979716.12     13928496.60
      1979301.65     13928221.01
#Sta/Elev= 30
  4167.0 1697.33  4200.1 1691.96  4220.9 1691.35  4251.3 1686.16  4267.0 1684.85
  4281.7 1686.19  4312.1 1680.85  4362.7 1675.45  4547.9 1663.68  4595.7 1659.13
  4611.9 1653.31  4612.4 1652.81  4620.0 1653.31  4626.1 1656.50  4643.7 1660.65
  4648.4 1660.24  4656.5 1662.21  4704.3 1662.16  4848.1 1659.72  4932.5 1659.93
  5057.6 1660.80  5108.7 1663.94  5149.0 1664.28  5172.2 1665.04  5222.9 1680.40
  5231.9 1680.63  5253.0 1684.35  5316.3 1697.64  5406.7 1707.04  5416.4 1707.60
#Mann=10,-1,0
  4167.0    0.07       0  4547.9   0.035       0  4611.9   0.035       0
  4620.0   0.035       0  4643.7    0.07       0  4704.3   0.035       0
  4848.1    0.07       0  4932.5   0.035       0  5149.0    0.07       0
  5406.7   0.035       0
Bank Sta=4611.9,4620
Exp/Cntr=0.3,0.1

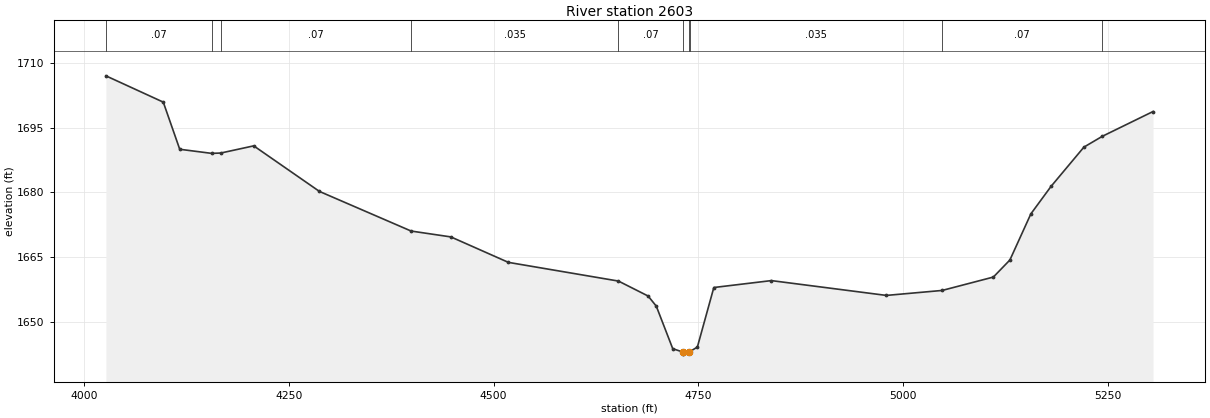
Type RM Length L Ch R = 1,2603,0,0,0
BEGIN DESCRIPTION:
Stream0065 T2
END DESCRIPTION:
XS GIS Cut Line= 3
      1980694.87     13928231.85      1979776.88     13928151.55
      1979420.98     13928114.66
#Sta/Elev= 30
  4026.3 1706.98  4096.4 1700.89  4116.5 1689.98  4155.5 1689.03  4166.7 1689.11
  4206.9 1690.77  4287.2 1680.22  4399.2 1671.05  4447.8 1669.69  4518.0 1663.80
  4652.5 1659.47  4688.7 1656.01  4698.7 1653.67  4718.8 1643.82  4730.9 1643.06
  4731.4 1642.56  4739.0 1643.06  4739.3 1643.10  4748.9 1644.20  4769.0 1657.98
  4839.3 1659.58  4979.8 1656.15  5047.9 1657.30  5110.5 1660.40  5130.7 1664.35
  5156.3 1675.02  5180.9 1681.37  5221.1 1690.47  5243.6 1692.98  5305.6 1698.72
#Mann=10,-1,0
  4026.3    0.07       0  4155.5   0.035       0  4166.7    0.07       0
  4399.2   0.035       0  4652.5    0.07       0  4730.9   0.035       0
  4739.0    0.07       0  4739.3   0.035       0  5047.9    0.07       0
  5243.6   0.035       0
Bank Sta=4730.9,4739
Exp/Cntr=0.3,0.1

Chan Stop Cuts=-1