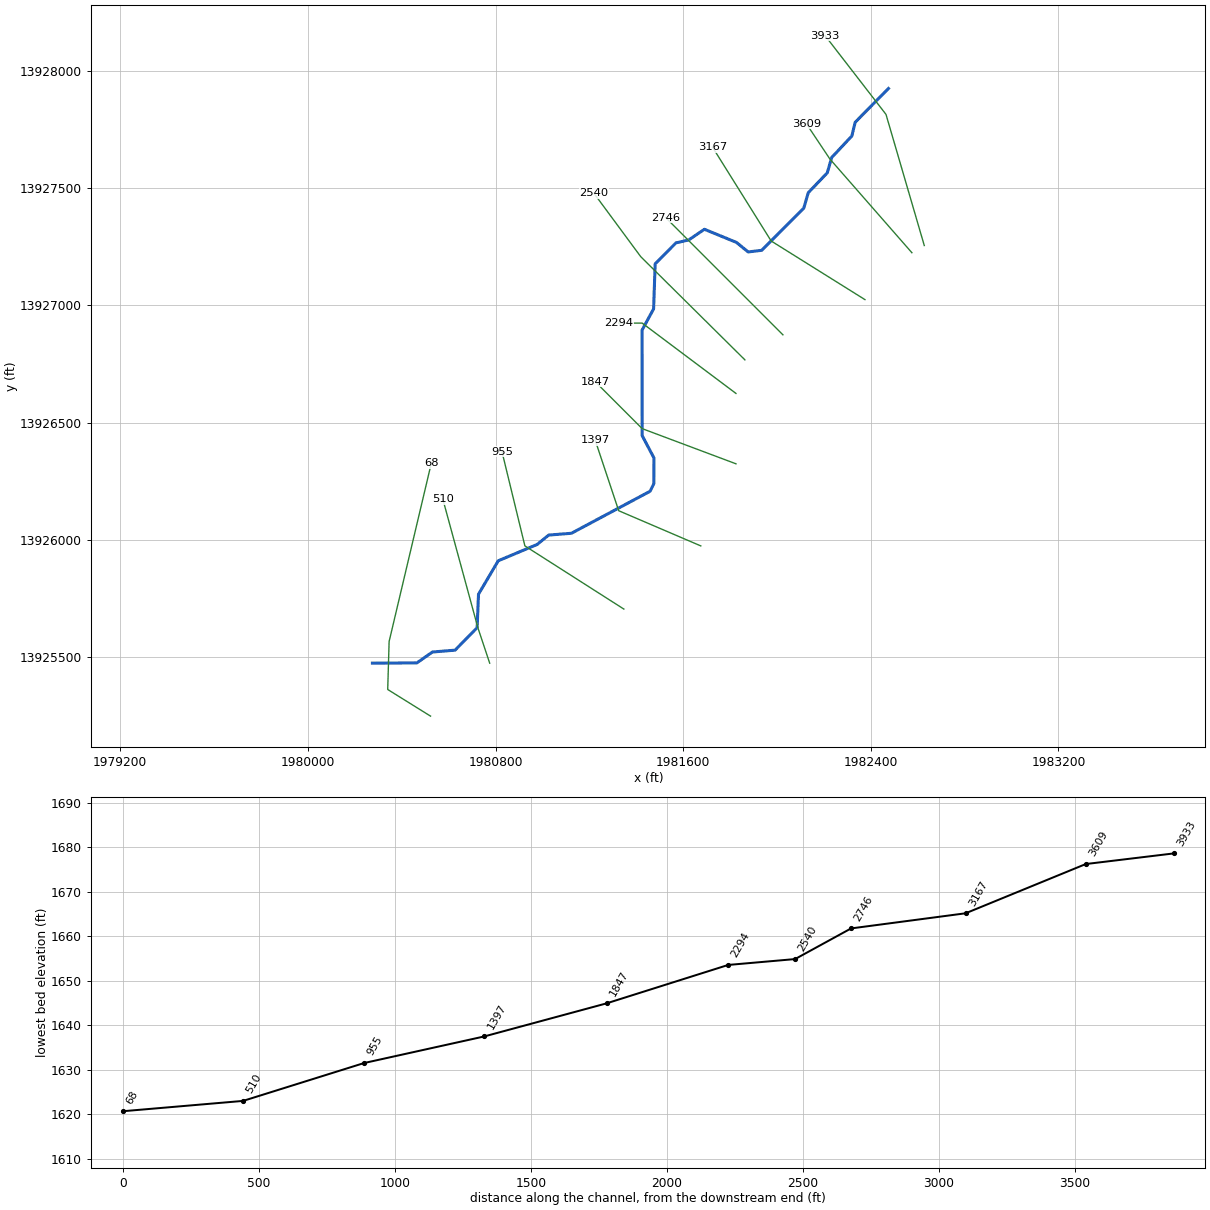
--- Stream0066.prj (project) ---

Proj Title=Stream0066 Base Level Engineering
Current Plan=p01
Default Exp/Contr=0.3,0.1
English Units
Geom File=g01
Flow File=f01
Plan File=p01
Y Axis Title=Elevation
X Axis Title(PF)=Main Channel Distance
X Axis Title(XS)=Station
BEGIN DESCRIPTION:
Stream0066
END DESCRIPTION:
DSS Export Rating Curves= 0
DSS Export Rating Curve Sorted= 0
DSS Export Volume Flow Curves= 0
DXF OffsetX= 0
DXF OffsetY= 0
DXF ScaleX= 1
DXF ScaleY= 10

--- Stream0066.p01 (plan) ---

Plan Title=Multiple Run
Short Identifier=Multiple
Geom File=g01
Flow File=f01
Subcritical Flow
K Sum by GR= 0
Std Step Tol= 0.01
Critical Tol= 0.01
Num of Std Step Trials= 20
Max Error Tol= 0.3
Flow Tol Ratio= 0.001
Split Flow NTrial= 30
Split Flow Tol= 0.02
Split Flow Ratio= 0.02
Log Output Level= 0
Friction Slope Method= 1
Unsteady Friction Slope Method= 2
Unsteady Bridges Friction Slope Method= 1
Parabolic Critical Depth
Global Vel Dist=  1 , 1 , 1
Global Log Level= 0
CheckData=True
Encroach Param= -1, 0, 0, 0
BEGIN DESCRIPTION:
Multiple Run
END DESCRIPTION:

--- Stream0066.f01 (steady flow) ---

Flow Title=Multiple
Program Version=4.10
Number of Profiles= 7
Profile Names=10-year,25-year,50-year,1pct_min,100-year,1pct_plu,500-year
River Rch & RM=Stream0066,Reach-1         ,3933
    1306    2283    3241    2232    4452    8884    8337
Boundary for River Rch & Prof#=Stream0066,Reach-1         , 1
Up Type= 0
Dn Type= 3
Dn Slope=0.008
Boundary for River Rch & Prof#=Stream0066,Reach-1         , 2
Up Type= 0
Dn Type= 3
Dn Slope=0.008
Boundary for River Rch & Prof#=Stream0066,Reach-1         , 3
Up Type= 0
Dn Type= 3
Dn Slope=0.008
Boundary for River Rch & Prof#=Stream0066,Reach-1         , 4
Up Type= 0
Dn Type= 3
Dn Slope=0.008
Boundary for River Rch & Prof#=Stream0066,Reach-1         , 5
Up Type= 0
Dn Type= 3
Dn Slope=0.008
Boundary for River Rch & Prof#=Stream0066,Reach-1         , 6
Up Type= 0
Dn Type= 3
Dn Slope=0.008
Boundary for River Rch & Prof#=Stream0066,Reach-1         , 7
Up Type= 0
Dn Type= 3
Dn Slope=0.008
DSS Import GetInterval= 0
DSS Import GetPeak= 0
DSS Import FillOption= 0

--- Stream0066.g01 (geometry) ---

Geom Title=Existing Conditions
Program Version=4.10

River Reach=Stream0066      ,Reach-1
Reach XY= 30
        1982475.       13927925.      1982333.15     13927781.05
      1982319.13     13927722.72      1982233.18     13927631.04
       1982214.2     13927565.33      1982133.18     13927481.04
      1982114.22     13927415.32      1981934.68     13927235.19
      1981876.74     13927228.31       1981827.2     13927268.85
      1981690.39     13927324.93      1981623.26     13927279.25
      1981568.93     13927266.87      1981480.45     13927177.47
      1981473.78     13926985.51      1981424.64     13926895.15
      1981425.07     13926445.03      1981475.23     13926350.07
      1981474.69     13926240.04      1981458.73     13926207.86
      1981123.42     13926028.83      1981026.58     13926021.17
      1980977.18     13925981.12      1980811.43     13925911.53
      1980727.25     13925769.07      1980721.46     13925626.46
      1980627.44     13925530.52      1980530.98     13925522.64
       1980464.5     13925476.21        1980275.       13925475.

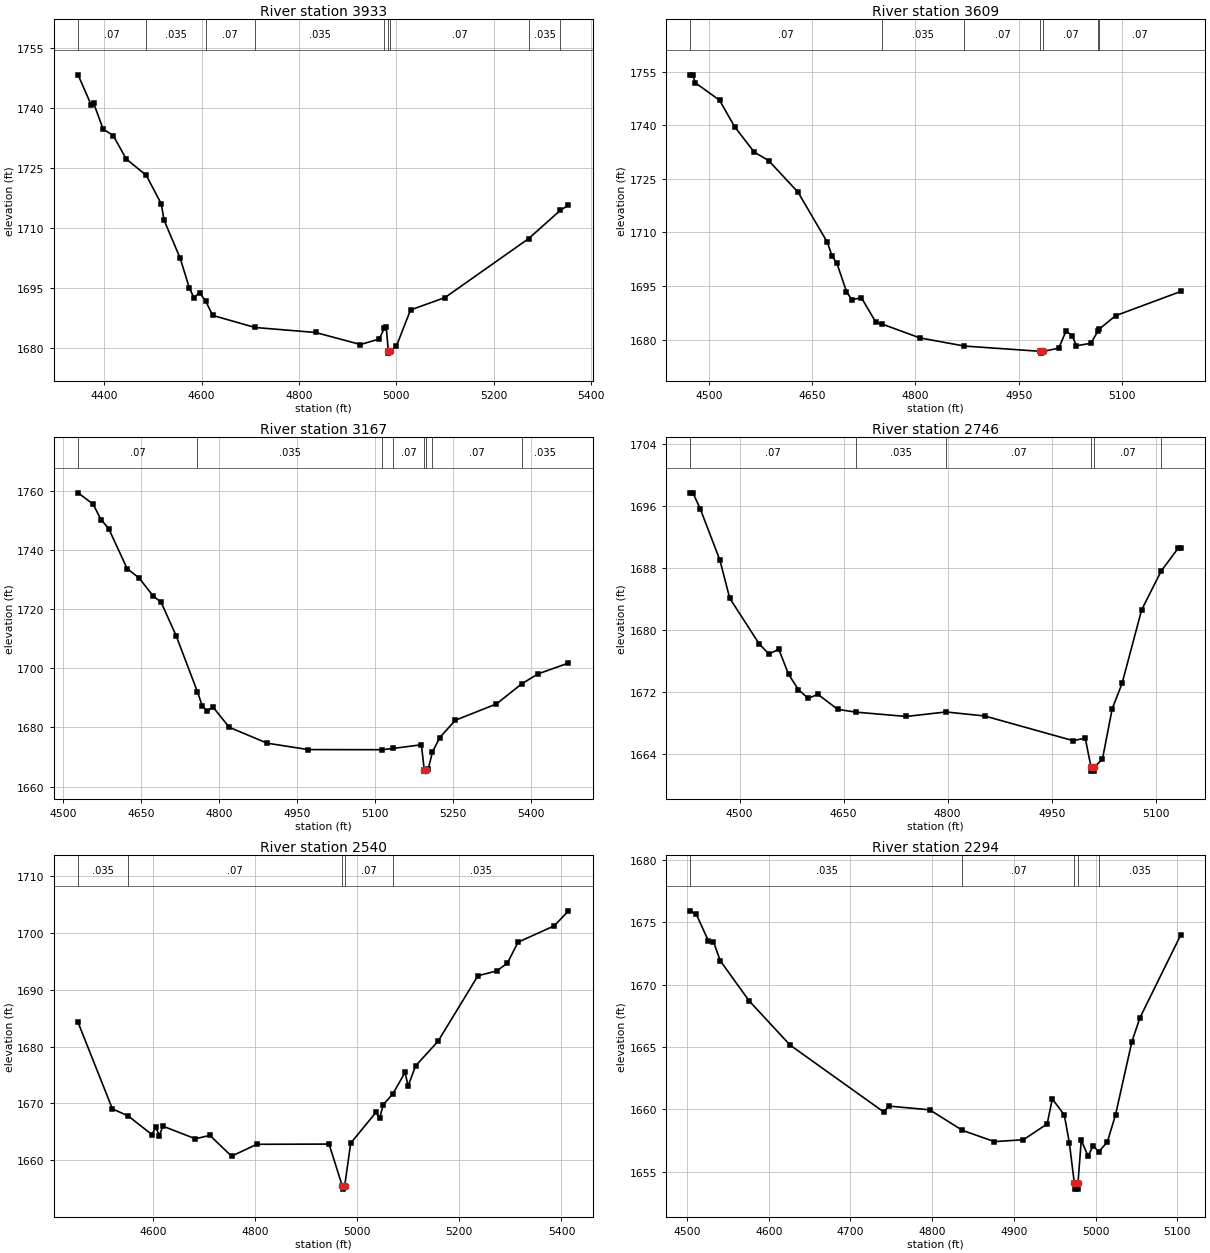
Type RM Length L Ch R = 1 ,3933    ,324,324,324
BEGIN DESCRIPTION:
Stream0066 9.0
END DESCRIPTION:
XS GIS Cut Line= 3
      1982627.83      13927255.6      1982464.62     13927814.66
      1982204.78     13928150.72
#Sta/Elev= 30
  4346.3 1748.21    4373 1740.76  4378.2 1741.18  4397.8 1734.63  4418.6 1733.03
  4445.1  1727.2  4486.3 1723.11  4517.3 1715.94  4522.8 1711.92  4555.9 1702.42
  4574.9 1694.93  4584.2 1692.54  4595.7 1693.75  4608.1 1691.73  4622.9 1688.09
  4709.7 1685.08  4834.1 1683.83  4926.3 1680.82  4964.8 1682.19  4975.4 1684.93
  4979.3 1685.11  4983.5 1679.17  4983.8 1678.67  4987.8 1679.17  5000.1 1680.43
  5029.1 1689.46  5099.8 1692.55  5271.6 1707.28  5336.8 1714.36  5353.5 1715.66
#Mann= 9 ,-1 , 0
  4346.3     .07       0  4486.3    .035       0  4608.1     .07       0
  4709.7    .035       0  4975.4     .07       0  4983.5     .05       0
  4987.8     .07       0  5271.6    .035       0  5336.8     .07       0
Bank Sta=4983.5,4987.8
XS Rating Curve= 0 ,0
Exp/Cntr=0.3,0.1

Type RM Length L Ch R = 1 ,3609    ,442,442,442
BEGIN DESCRIPTION:
Stream0066 8.0
END DESCRIPTION:
XS GIS Cut Line= 3
        1982575.       13927225.        1982225.       13927625.
      1982124.99     13927775.02
#Sta/Elev= 30
  4473.5 1754.07  4476.8 1754.07  4480.6 1751.83  4515.7 1746.97  4537.6 1739.56
    4566 1732.47  4586.9 1730.11  4629.6 1721.27  4672.3 1707.22    4679  1703.4
  4686.1 1701.35  4699.9  1693.5  4707.5 1691.24  4721.7 1691.73  4742.6  1684.9
    4751 1684.45  4806.2 1680.55  4870.9 1678.26  4981.5 1676.78  4981.8 1676.28
  4985.8 1676.78    5008 1677.67  5018.5  1682.4  5027.5  1681.2  5033.5 1678.34
  5054.6 1679.02  5064.6 1682.35  5066.3 1682.92  5090.6 1686.75  5185.3 1693.53
#Mann= 7 ,-1 , 0
  4473.5     .07       0    4751    .035       0  4870.9     .07       0
  4981.5     .05       0  4985.8     .07       0  5064.6    .035       0
  5066.3     .07       0
Bank Sta=4981.5,4985.8
XS Rating Curve= 0 ,0
Exp/Cntr=0.3,0.1

Type RM Length L Ch R = 1 ,3167    ,421,421,421
BEGIN DESCRIPTION:
Stream0066 7.0
END DESCRIPTION:
XS GIS Cut Line= 3
      1982374.98     13927025.01        1981975.       13927275.
      1981724.99     13927675.02
#Sta/Elev= 30
  4528.6 1759.27  4557.5 1755.44  4572.8 1750.23  4587.5 1747.18  4622.9 1733.69
  4645.9 1730.51    4673 1724.43  4688.4 1722.26  4717.3 1710.97  4758.2 1692.03
  4767.4 1687.35  4776.2 1685.47  4788.6 1686.78  4819.3 1680.04  4892.4 1674.65
  4971.4 1672.49  5113.3 1672.45  5134.8 1672.88    5189 1674.12  5194.5 1665.71
  5194.8 1665.21  5198.8 1665.71  5202.5 1666.06    5210 1671.53  5224.3 1676.56
  5254.4 1682.41  5333.4 1687.92  5381.9 1694.69    5413 1698.04    5472 1701.75
#Mann= 8 ,-1 , 0
  4528.6     .07       0  4758.2    .035       0  5113.3     .07       0
  5134.8     .07       0  5194.5     .05       0  5198.8     .07       0
    5210     .07       0  5381.9    .035       0
Bank Sta=5194.5,5198.8
XS Rating Curve= 0 ,0
Exp/Cntr=0.3,0.1

Type RM Length L Ch R = 1 ,2746    ,206,206,206
BEGIN DESCRIPTION:
Stream0066 6.0
END DESCRIPTION:
XS GIS Cut Line= 3
        1982025.       13926875.        1981625.       13927275.
      1981525.01     13927374.99
#Sta/Elev= 30
  4429.2 1697.65  4432.7 1697.65  4443.3 1695.59  4471.6 1688.99  4485.8 1684.08
  4528.2 1678.21  4542.3 1676.88  4556.5 1677.51  4570.6 1674.29  4584.8 1672.31
  4598.9 1671.18    4613  1671.7  4641.3 1669.77  4667.3 1669.41  4740.3 1668.85
  4797.5 1669.43  4853.5 1668.91  4980.7 1665.74  4998.4 1666.05  5006.8 1662.31
  5007.1 1661.81  5010.9 1661.81  5011.2 1662.31  5023.2 1663.36  5037.3 1669.85
  5051.5 1673.11  5079.7 1682.58    5108  1687.6  5132.8 1690.56  5136.3 1690.56
#Mann= 6 ,-1 , 0
  4429.2     .07       0  4667.3    .035       0  4797.5     .07       0
  5006.8     .05       0  5011.2     .07       0    5108    .035       0
Bank Sta=5006.8,5011.2
XS Rating Curve= 0 ,0
Exp/Cntr=0.3,0.1

Type RM Length L Ch R = 1 ,2540    ,246,246,246
BEGIN DESCRIPTION:
Mapping XS ee15715d
END DESCRIPTION:
XS GIS Cut Line= 3
      1981863.09     13926768.14      1981418.86     13927208.19
      1981219.99     13927477.66
#Sta/Elev= 30
  4453.5 1684.27  4520.7 1669.05  4551.6  1667.8  4598.4  1664.5  4605.5 1665.86
  4612.6 1664.35  4619.7    1666  4683.3 1663.78  4711.6 1664.38    4754 1660.72
  4803.5 1662.81  4944.9 1662.85    4971 1655.42  4971.3 1654.92  4975.4 1655.42
  4987.3 1663.01  5036.8 1668.44  5043.9  1667.4    5051 1669.78    5070 1671.72
  5093.6 1675.46  5099.8 1673.09  5114.4 1676.62  5158.3 1680.95  5236.4 1692.48
  5273.2 1693.33  5294.1 1694.71  5314.9 1698.39  5385.9 1701.27  5413.7 1703.91
#Mann= 5 ,-1 , 0
  4453.5    .035       0  4551.6     .07       0    4971     .05       0
  4975.4     .07       0    5070    .035       0
Bank Sta=4971,4975.4
XS Rating Curve= 0 ,0
Exp/Cntr=0.3,0.1

Type RM Length L Ch R = 1 ,2294    ,447,447,447
BEGIN DESCRIPTION:
Stream0066 5.0
END DESCRIPTION:
XS GIS Cut Line= 3
      1981824.99     13926625.01        1981425.       13926925.
      1981324.99       13926925.
#Sta/Elev= 30
  4504.3 1675.92  4511.6 1675.63  4526.2 1673.51  4532.4 1673.46  4540.7 1671.92
  4576.2 1668.69  4626.2 1665.15  4740.7 1659.79    4747 1660.26    4797 1659.96
  4837.1 1658.31  4876.2 1657.41  4911.6 1657.56  4940.7 1658.83    4947 1660.83
  4961.6 1659.56  4967.8 1657.33  4973.9  1654.1  4974.3  1653.6  4978.1  1653.6
  4978.4  1654.1  4982.4 1657.52  4990.7 1656.26    4997 1657.08  5003.7 1656.59
  5014.3 1657.38  5024.3 1659.55  5044.3 1665.42  5054.3 1667.36  5104.3 1674.01
#Mann= 5 ,-1 , 0
  4504.3    .035       0  4837.1     .07       0  4973.9     .05       0
  4978.4     .07       0  5003.7    .035       0
Bank Sta=4973.9,4978.4
XS Rating Curve= 0 ,0
Exp/Cntr=0.3,0.1

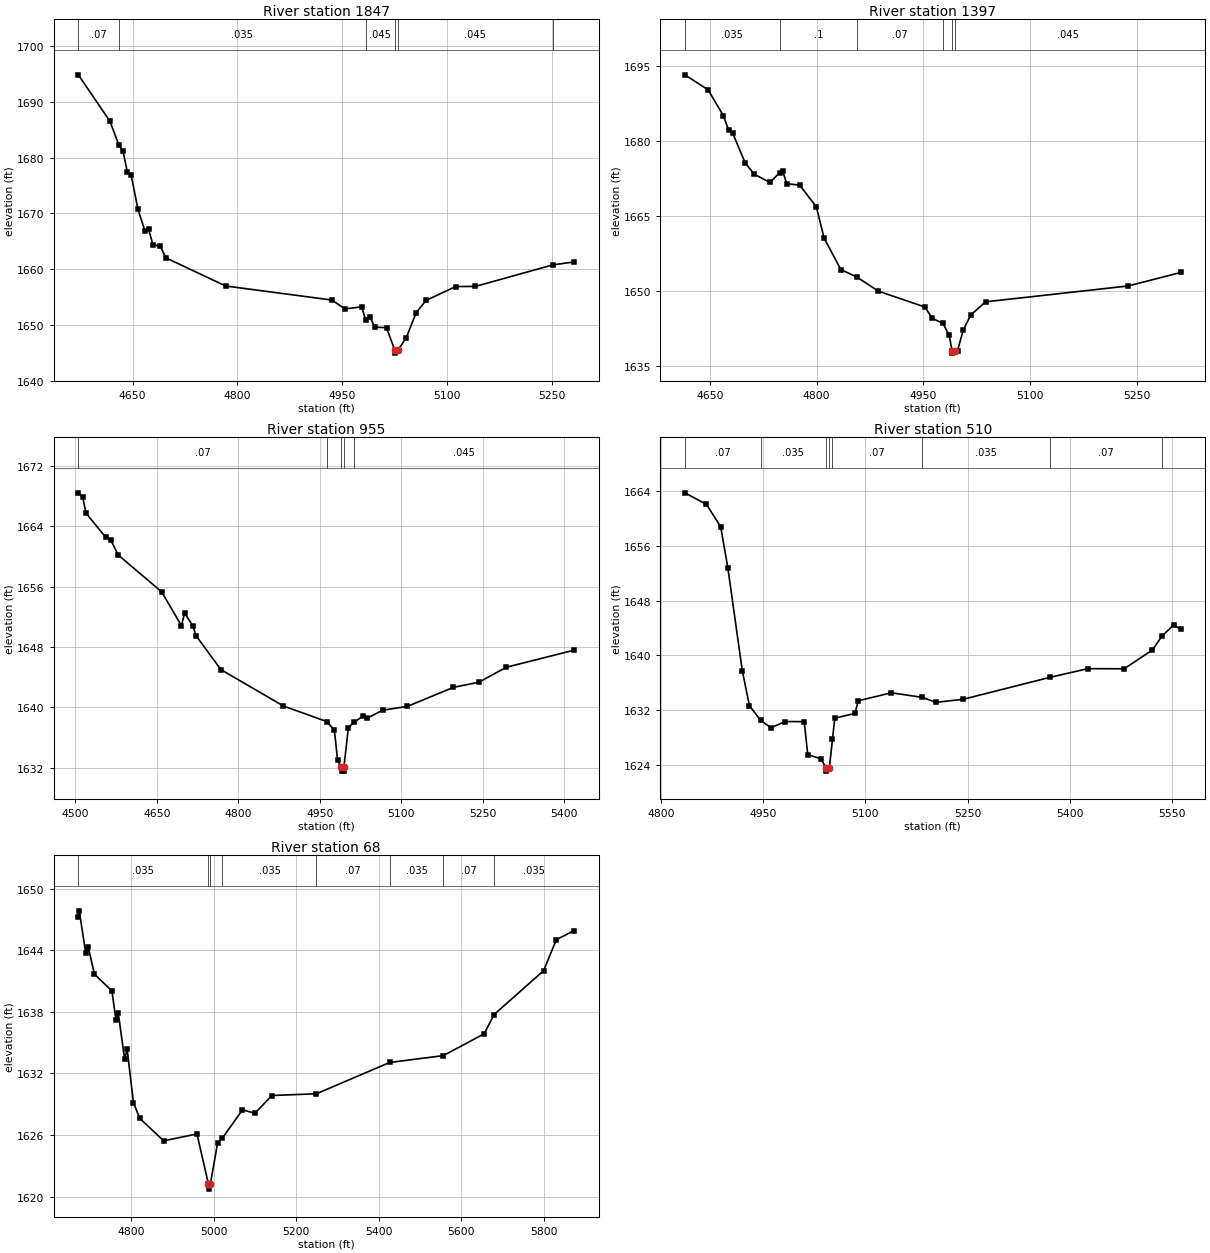
Type RM Length L Ch R = 1 ,1847    ,450,450,450
BEGIN DESCRIPTION:
Stream0066 4.0
END DESCRIPTION:
XS GIS Cut Line= 3
      1981824.96     13926325.01        1981425.       13926475.
        1981225.       13926675.
#Sta/Elev= 30
  4572.3 1694.83  4617.6  1686.5  4630.5  1682.2  4636.3 1681.13  4642.6 1677.36
  4647.9 1676.88  4657.7 1670.73  4667.5 1666.93  4672.8 1667.23  4679.1 1664.39
  4689.7 1664.11  4697.7 1662.04  4783.2    1657  4935.4 1654.48  4954.1 1652.89
  4978.1 1653.26  4983.6 1650.93  4989.7 1651.52  4996.8 1649.62  5013.6 1649.53
  5025.5 1645.47  5025.8 1644.97    5030 1645.47  5041.9 1647.75    5056 1652.19
  5070.2 1654.41  5112.6  1656.9  5140.9 1656.92  5251.4 1660.77  5282.3 1661.31
#Mann= 6 ,-1 , 0
  4572.3     .07       0  4630.5    .035       0  4983.6    .045       0
  5025.5    .045       0    5030    .045       0  5251.4    .035       0
Bank Sta=5025.5,5030
XS Rating Curve= 0 ,0
Exp/Cntr=0.3,0.1

Type RM Length L Ch R = 1 ,1397    ,442,442,442
BEGIN DESCRIPTION:
Stream0066 3.0
END DESCRIPTION:
XS GIS Cut Line= 3
      1981674.98     13925975.01        1981325.       13926125.
        1981225.     13926425.01
#Sta/Elev= 30
  4614.7 1693.27  4647.3 1690.29  4669.1 1685.06  4676.3 1682.17  4681.8 1681.67
  4699.9 1675.53  4712.6 1673.35  4734.4 1671.71  4748.1 1673.67  4752.5 1673.95
  4757.9 1671.44  4776.1  1671.2  4799.6 1666.83  4810.5 1660.58  4834.1 1654.26
  4856.8 1652.75  4886.7 1649.95  4951.9 1646.78  4962.8 1644.49  4977.7 1643.47
  4986.4 1641.09  4990.4 1638.03  4990.8 1637.53    4995 1638.03  4998.1 1638.03
    5006  1642.1  5016.5 1645.14  5037.6 1647.81  5237.9 1650.98  5311.7 1653.68
#Mann= 6 ,-1 , 0
  4614.7    .035       0  4748.1      .1       0  4856.8     .07       0
  4977.7    .045       0  4990.4    .045       0    4995    .045       0
Bank Sta=4990.4,4995
XS Rating Curve= 0 ,0
Exp/Cntr=0.3,0.1

Type RM Length L Ch R = 1 ,955     ,445,445,445
BEGIN DESCRIPTION:
Stream0066 2.0
END DESCRIPTION:
XS GIS Cut Line= 3
      1981346.85     13925705.74        1980925.       13925975.
      1980827.48     13926376.26
#Sta/Elev= 30
  4505.3 1668.43  4513.3 1667.88  4519.4 1665.75  4555.6 1662.54  4564.9 1662.22
  4578.7  1660.2  4658.9  1655.3  4695.2 1650.83  4701.2 1652.49  4716.4 1650.79
  4722.3 1649.48    4768    1645  4883.1 1640.18  4963.3 1638.11    4977 1636.98
  4982.9 1632.99  4989.9 1632.05  4990.2 1631.55  4994.2 1631.55  4994.5 1632.05
  5002.8 1637.33  5013.2 1638.03  5029.2 1638.82  5036.6 1638.53  5065.8 1639.62
  5111.6 1640.13  5196.2 1642.65  5243.1 1643.33  5293.9 1645.32  5418.7 1647.58
#Mann= 5 ,-1 , 0
  4505.3     .07       0  4963.3    .035       0  4989.9    .035       0
  4994.5    .035       0  5013.2    .045       0
Bank Sta=4989.9,4994.5
XS Rating Curve= 0 ,0
Exp/Cntr=0.3,0.1

Type RM Length L Ch R = 1 ,510     ,442,442,442
BEGIN DESCRIPTION:
Stream0066 1.0
END DESCRIPTION:
XS GIS Cut Line= 3
      1980775.01     13925474.96        1980725.       13925625.
      1980575.01     13926174.96
#Sta/Elev= 30
  4834.8 1663.78  4866.5 1662.11  4887.5 1658.81  4898.1 1652.75  4919.2 1637.76
  4929.7 1632.62  4946.1 1630.47  4961.3  1629.4  4982.4  1630.3  5010.2 1630.28
  5015.4 1625.46  5034.4 1624.85  5042.4 1623.54  5042.8 1623.04  5047.1 1623.54
  5051.7 1627.71  5055.1  1630.8  5084.5 1631.48  5089.7 1633.34  5138.1 1634.51
  5183.3 1633.84  5203.7 1633.11  5243.4 1633.55  5370.7 1636.76  5426.6 1638.04
  5480.1 1638.02  5521.6 1640.78  5535.8 1642.83  5552.7 1644.43    5563 1643.84
#Mann= 8 ,-1 , 0
  4834.8     .07       0  4946.1    .035       0  5042.4    .035       0
  5047.1    .035       0  5051.7     .07       0  5183.3    .035       0
  5370.7     .07       0  5535.8    .035       0
Bank Sta=5042.4,5047.1
XS Rating Curve= 0 ,0
Exp/Cntr=0.3,0.1

Type RM Length L Ch R = 1 ,68      ,0,0,0
BEGIN DESCRIPTION:
Stream0066 0.0
END DESCRIPTION:
XS GIS Cut Line= 4
      1980522.77     13925249.24       1980340.2      13925362.8
      1980346.17     13925567.42       1980525.9     13926326.93
#Sta/Elev= 30
  4672.8  1647.3  4675.1 1647.86  4690.5 1643.77  4696.4 1644.38  4711.7 1641.69
  4754.2 1640.04  4763.7 1637.23  4769.6 1637.85  4784.9 1633.38  4790.8 1634.39
  4806.2 1629.16  4821.5 1627.62  4879.4 1625.43    4960  1626.1  4987.7 1621.22
    4988 1620.72  4992.4 1621.22  5010.1 1625.26  5021.5  1625.7  5070.1 1628.45
  5100.3 1628.12  5141.4 1629.85  5249.3 1630.02  5426.3 1633.07  5556.3 1633.74
  5655.2 1635.87    5679 1637.74    5799 1642.02  5829.9 1645.05    5873 1645.93
#Mann= 8 ,-1 , 0
  4672.8    .035       0  4987.7    .035       0  4992.4    .035       0
  5021.5    .035       0  5249.3     .07       0  5426.3    .035       0
  5556.3     .07       0    5679    .035       0
Bank Sta=4987.7,4992.4
XS Rating Curve= 0 ,0
Exp/Cntr=0.3,0.1

Chan Stop Cuts=-1
Use User Specified Reach Order=0
Composite Channel Slope=5