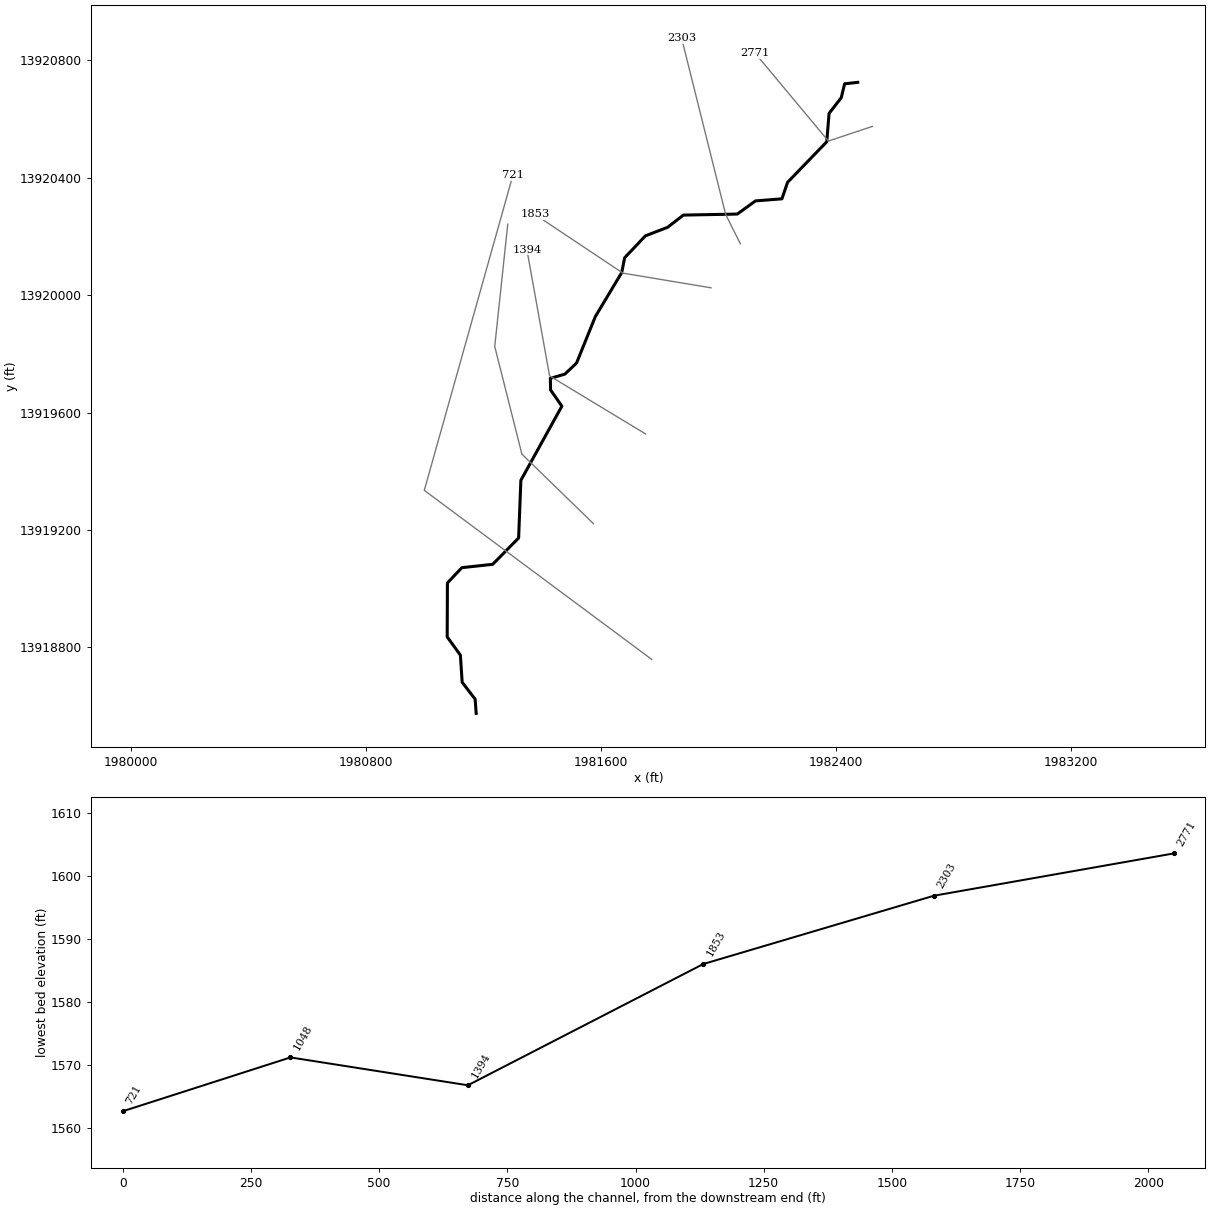
--- Stream0067.prj (project) ---

Proj Title=Stream0067 Base Level Engineering
Current Plan=p01
Default Exp/Contr=0.3,0.1
English Units
Geom File=g01
Flow File=f01
Plan File=p01
Y Axis Title=Elevation
X Axis Title(PF)=Main Channel Distance
X Axis Title(XS)=Station
BEGIN DESCRIPTION:
Stream0067
END DESCRIPTION:
DSS Export Rating Curves= 0
DSS Export Rating Curve Sorted= 0
DSS Export Volume Flow Curves= 0
DXF OffsetX= 0
DXF OffsetY= 0
DXF ScaleX= 1
DXF ScaleY= 10

--- Stream0067.p01 (plan) ---

Plan Title=Multiple Run
Short Identifier=Multiple
Geom File=g01
Flow File=f01
Subcritical Flow
K Sum by GR= 0
Std Step Tol= 0.01
Critical Tol= 0.01
Num of Std Step Trials= 20
Max Error Tol= 0.3
Flow Tol Ratio= 0.001
Split Flow NTrial= 30
Split Flow Tol= 0.02
Split Flow Ratio= 0.02
Log Output Level= 0
Friction Slope Method= 1
Unsteady Friction Slope Method= 2
Unsteady Bridges Friction Slope Method= 1
Parabolic Critical Depth
Global Vel Dist=  1 , 1 , 1
Global Log Level= 0
CheckData=True
Encroach Param= -1, 0, 0, 0
BEGIN DESCRIPTION:
Multiple Run
END DESCRIPTION:

--- Stream0067.f01 (steady flow) ---

Flow Title=Multiple
Number of Profiles=7
Profile Names=10-year,25-year,50-year,1pct_min,100-year,1pct_plu,500-year
River Rch & RM= Stream0067,Reach-1,2771
     679    1145    1589    1072    2140    4270    3844
Boundary for River Rch & Prof#=Stream0067,Reach-1,1
Up Type=0
Dn Type=3
Dn Slope=0.005
Boundary for River Rch & Prof#=Stream0067,Reach-1,2
Up Type=0
Dn Type=3
Dn Slope=0.005
Boundary for River Rch & Prof#=Stream0067,Reach-1,3
Up Type=0
Dn Type=3
Dn Slope=0.005
Boundary for River Rch & Prof#=Stream0067,Reach-1,4
Up Type=0
Dn Type=3
Dn Slope=0.005
Boundary for River Rch & Prof#=Stream0067,Reach-1,5
Up Type=0
Dn Type=3
Dn Slope=0.005
Boundary for River Rch & Prof#=Stream0067,Reach-1,6
Up Type=0
Dn Type=3
Dn Slope=0.005
Boundary for River Rch & Prof#=Stream0067,Reach-1,7
Up Type=0
Dn Type=3
Dn Slope=0.005

--- Stream0067.g01 (geometry) ---

Geom Title=Existing Conditions
Program Version=4.10

River Reach=Stream0067      ,Reach-1
Reach XY= 30
        1982475.       13920725.      1982430.28      13920720.1
      1982418.96       13920673.      1982377.31     13920619.06
      1982369.48     13920522.57       1982235.9     13920384.38
      1982216.66     13920328.16      1982126.67     13920321.11
       1982064.5     13920276.22      1981880.93     13920272.76
      1981827.17     13920231.14      1981751.48     13920202.01
      1981680.83     13920127.31      1981670.81     13920076.74
      1981581.08      13919927.2      1981516.92     13919768.68
      1981477.08     13919730.89      1981427.69     13919716.49
      1981428.43     13919677.01      1981466.92     13919621.72
      1981327.24     13919369.07      1981319.55     13919172.53
      1981231.19     13919082.86      1981126.25     13919071.49
      1981076.97     13919019.35      1981076.22      13918835.5
      1981121.15      13918773.4      1981127.23     13918680.92
      1981171.36     13918623.49        1981175.       13918575.

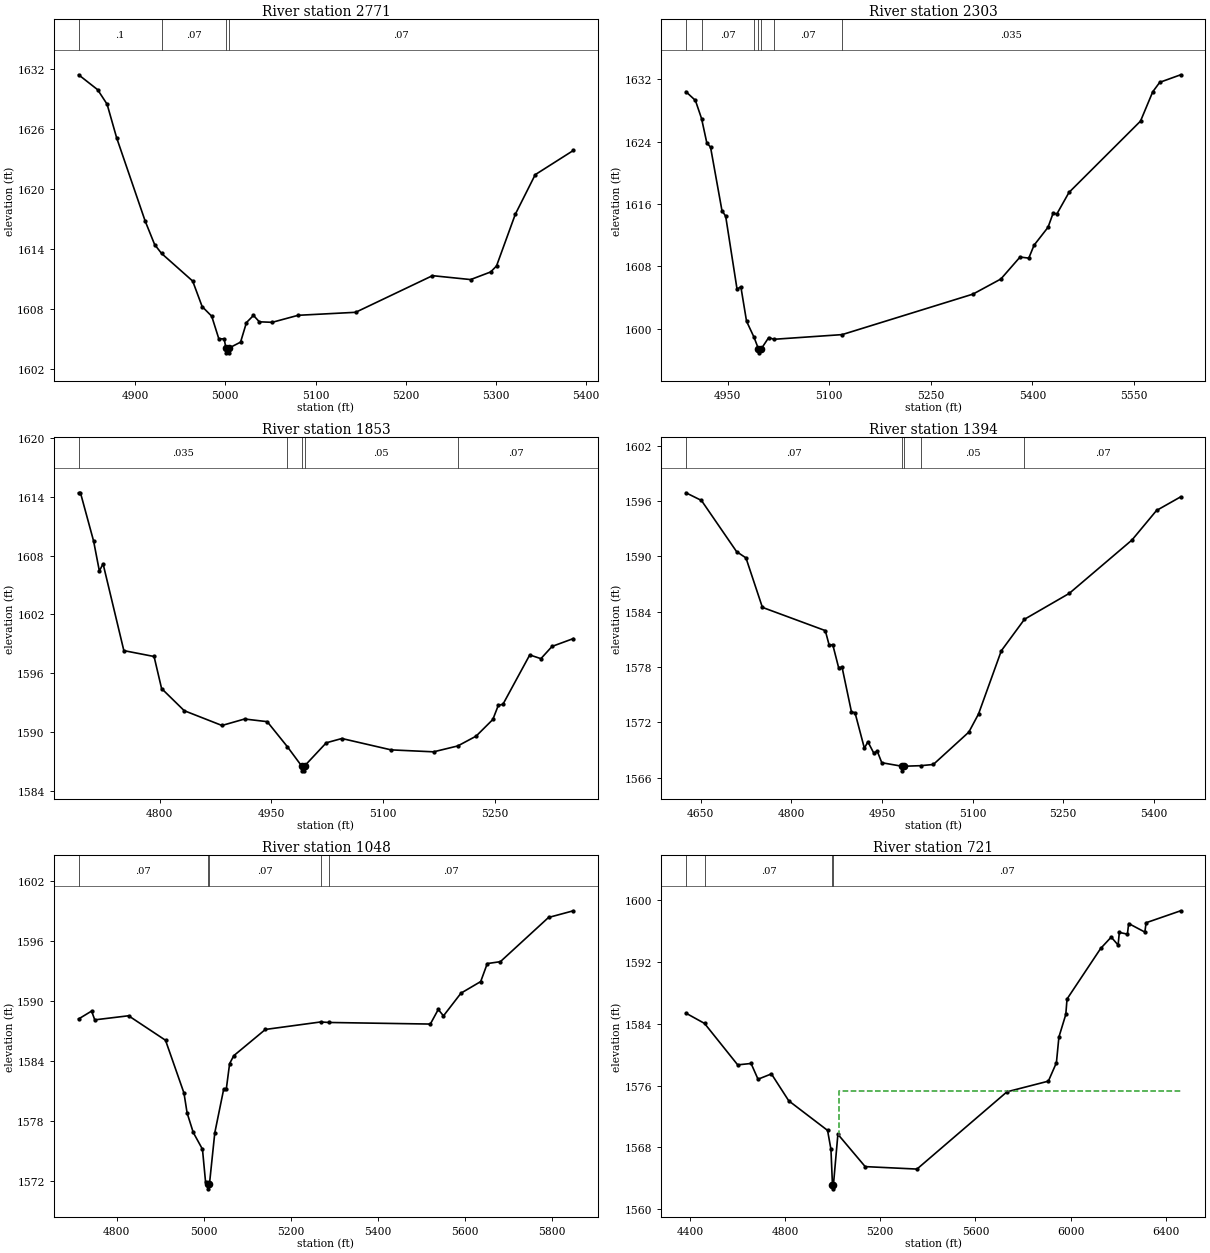
Type RM Length L Ch R = 1 ,2771    ,468,468,468
BEGIN DESCRIPTION:
Stream0067 4.0
END DESCRIPTION:
XS GIS Cut Line= 3
        1982525.       13920575.        1982375.       13920525.
      1982125.02     13920824.98
#Sta/Elev= 30
  4837.3 1631.41  4858.4 1629.92  4868.9 1628.47  4879.5 1625.11  4911.1  1616.8
  4921.6 1614.45  4929.3 1613.56  4963.8  1610.8  4974.3 1608.25  4984.9 1607.29
  4992.8 1605.03  4998.7 1605.03  5000.6 1604.13  5000.8 1603.63  5004.3 1603.63
  5004.6 1604.13  5016.9  1604.7  5023.4 1606.65  5031.2 1607.37  5037.7 1606.73
    5052 1606.68  5080.7 1607.38  5144.5 1607.68  5229.7 1611.34    5272 1610.95
  5294.2 1611.71  5300.7 1612.31  5321.5 1617.47  5343.6 1621.43  5385.9 1623.85
#Mann= 4 ,-1 , 0
  4837.3      .1       0  4929.3     .07       0  5000.6     .05       0
  5004.6     .07       0
Bank Sta=5000.6,5004.6
XS Rating Curve= 0 ,0
Exp/Cntr=0.3,0.1

Type RM Length L Ch R = 1 ,2303    ,450,450,450
BEGIN DESCRIPTION:
Stream0067 3.0
END DESCRIPTION:
XS GIS Cut Line= 3
      1982075.02     13920174.96        1982025.       13920275.
        1981875.     13920874.99
#Sta/Elev= 30
  4888.6 1630.43  4902.6 1629.31  4911.7 1626.98  4919.4 1623.88    4925 1623.29
  4941.8 1615.17  4947.3 1614.44  4964.1 1605.06  4969.7 1605.39  4978.1 1600.96
  4989.2 1598.89  4995.7  1597.4  4995.9  1596.9  4999.7  1597.4  5010.8 1598.86
  5018.6 1598.64  5119.2 1599.24  5312.3 1604.44  5353.5 1606.38  5381.8  1609.2
  5394.7 1609.06  5402.5 1610.72  5423.1 1613.02  5430.8 1614.87    5436 1614.71
    5454 1617.49  5559.6 1626.65  5577.7 1630.42    5588 1631.63  5618.9  1632.6
#Mann= 7 ,-1 , 0
  4888.6      .1       0  4911.7     .07       0  4989.2     .05       0
  4995.7     .05       0  4999.7     .05       0  5018.6     .07       0
  5119.2    .035       0
Bank Sta=4995.7,4999.7
XS Rating Curve= 0 ,0
Exp/Cntr=0.3,0.1

Type RM Length L Ch R = 1 ,1853    ,459,459,459
BEGIN DESCRIPTION:
Stream0067 2.0
END DESCRIPTION:
XS GIS Cut Line= 3
      1981974.97       13920025.        1981675.       13920075.
      1981374.97     13920275.02
#Sta/Elev= 30
  4691.2 1614.41  4693.7 1614.41  4711.4 1609.47  4719.1 1606.43  4724.1 1607.16
    4752  1598.3  4792.6  1597.7  4802.7 1594.43  4833.1 1592.17  4883.8 1590.66
  4914.2 1591.32  4944.6 1591.05  4971.7 1588.49  4990.8 1586.53    4991 1586.03
  4994.5 1586.03  4994.8 1586.53  5023.9 1588.89  5044.9 1589.33    5111 1588.17
  5168.1 1587.97  5200.6 1588.57  5225.2 1589.57  5247.7 1591.27  5255.2 1592.74
  5261.2 1592.81  5297.3 1597.86  5312.3 1597.48  5327.3 1598.73  5355.9 1599.53
#Mann= 5 ,-1 , 0
  4691.2    .035       0  4971.7     .05       0  4990.8     .05       0
  4994.8     .05       0  5200.6     .07       0
Bank Sta=4990.8,4994.8
XS Rating Curve= 0 ,0
Exp/Cntr=0.3,0.1

Type RM Length L Ch R = 1 ,1394    ,346,346,346
BEGIN DESCRIPTION:
Stream0067 1.0
END DESCRIPTION:
XS GIS Cut Line= 3
      1981752.42     13919526.91        1981425.       13919725.
      1981347.88     13920154.35
#Sta/Elev= 30
  4625.4 1596.89  4651.1 1596.06  4709.3 1590.51  4724.8 1589.83    4752 1584.47
  4856.1 1581.95  4862.6 1580.35  4868.4 1580.44  4878.1 1577.95  4883.9 1577.97
  4899.4 1573.14  4905.3 1573.05  4920.8  1569.2  4926.6  1569.9  4936.3 1568.68
  4942.1 1568.88  4949.6 1567.63  4982.8 1567.25  4983.1 1566.75  4986.8 1567.25
  5014.2 1567.31  5034.9 1567.44  5093.7 1570.95  5109.7 1572.91  5147.4 1579.76
  5185.8 1583.18  5259.8 1585.98  5363.7 1591.77  5404.3 1594.97  5444.3 1596.45
#Mann= 5 ,-1 , 0
  4625.4     .07       0  4982.8     .05       0  4986.8     .07       0
  5014.2     .05       0  5185.8     .07       0
Bank Sta=4982.8,4986.8
XS Rating Curve= 0 ,0
Exp/Cntr=0.3,0.1

Type RM Length L Ch R = 1 ,1048    ,327,327,327
BEGIN DESCRIPTION:
Stream0067 0.0
END DESCRIPTION:
XS GIS Cut Line= 4
      1981574.16     13919221.76      1981330.74     13919458.31
      1981238.17     13919825.17      1981282.56     13920241.73
#Sta/Elev= 30
  4712.9 1588.17  4742.8 1588.96    4750 1588.08  4827.7 1588.49  4912.6 1586.04
    4955 1580.76  4962.2 1578.77  4976.3 1576.82  4997.5 1575.14  5004.6 1571.86
  5009.6 1571.68  5009.9 1571.18  5013.6 1571.68  5025.8 1576.78  5046.4 1581.18
  5052.3 1581.18  5059.9 1583.71  5069.5  1584.5    5142 1587.12    5269 1587.87
  5287.2 1587.82    5521 1587.66  5539.2 1589.12  5551.2 1588.48  5591.4 1590.75
  5636.7 1591.91  5651.8 1593.71  5681.9  1593.9  5792.5 1598.32  5849.6 1598.99
#Mann= 5 ,-1 , 0
  4712.9     .07       0  5009.6     .05       0  5013.6     .07       0
    5269     .05       0  5287.2     .07       0
Bank Sta=5009.6,5013.6
XS Rating Curve= 0 ,0
Exp/Cntr=0.3,0.1

Type RM Length L Ch R = 1 ,721     ,0,0,0
BEGIN DESCRIPTION:
Stream0067 5.0
END DESCRIPTION:
XS GIS Cut Line= 3
      1981773.01      13918758.9      1980998.18     13919334.89
      1981299.89     13920408.01
#Sta/Elev= 30
  4382.9 1585.38  4461.1 1584.05  4600.6 1578.68  4656.9 1578.86  4686.1 1576.82
  4742.4 1577.51  4815.4 1574.02  4978.5 1570.19  4992.7 1567.74  4999.1 1563.12
  4999.3 1562.62  5003.1 1563.12  5021.9 1569.69  5136.6  1565.5  5354.4 1565.18
  5732.8 1575.19  5906.8 1576.57  5940.6 1578.95  5951.2 1582.29  5980.1 1585.21
  5985.3 1587.21  6126.7 1593.76  6171.1 1595.23    6200  1594.2  6205.2 1595.84
  6239.2 1595.61  6244.4 1596.99  6312.5 1595.88  6317.7 1597.09  6463.1 1598.64
#Mann= 4 ,-1 , 0
  4382.9      .1       0  4461.1     .07       0  4999.1     .05       0
  5003.1     .07       0
#XS Ineff= 2 , 0
                         5028.59         1575.33
Permanent Ineff=
       F       F
Bank Sta=4999.1,5003.1
XS Rating Curve= 0 ,0
Exp/Cntr=0.3,0.1

Chan Stop Cuts=-1
Use User Specified Reach Order=0
Composite Channel Slope=5