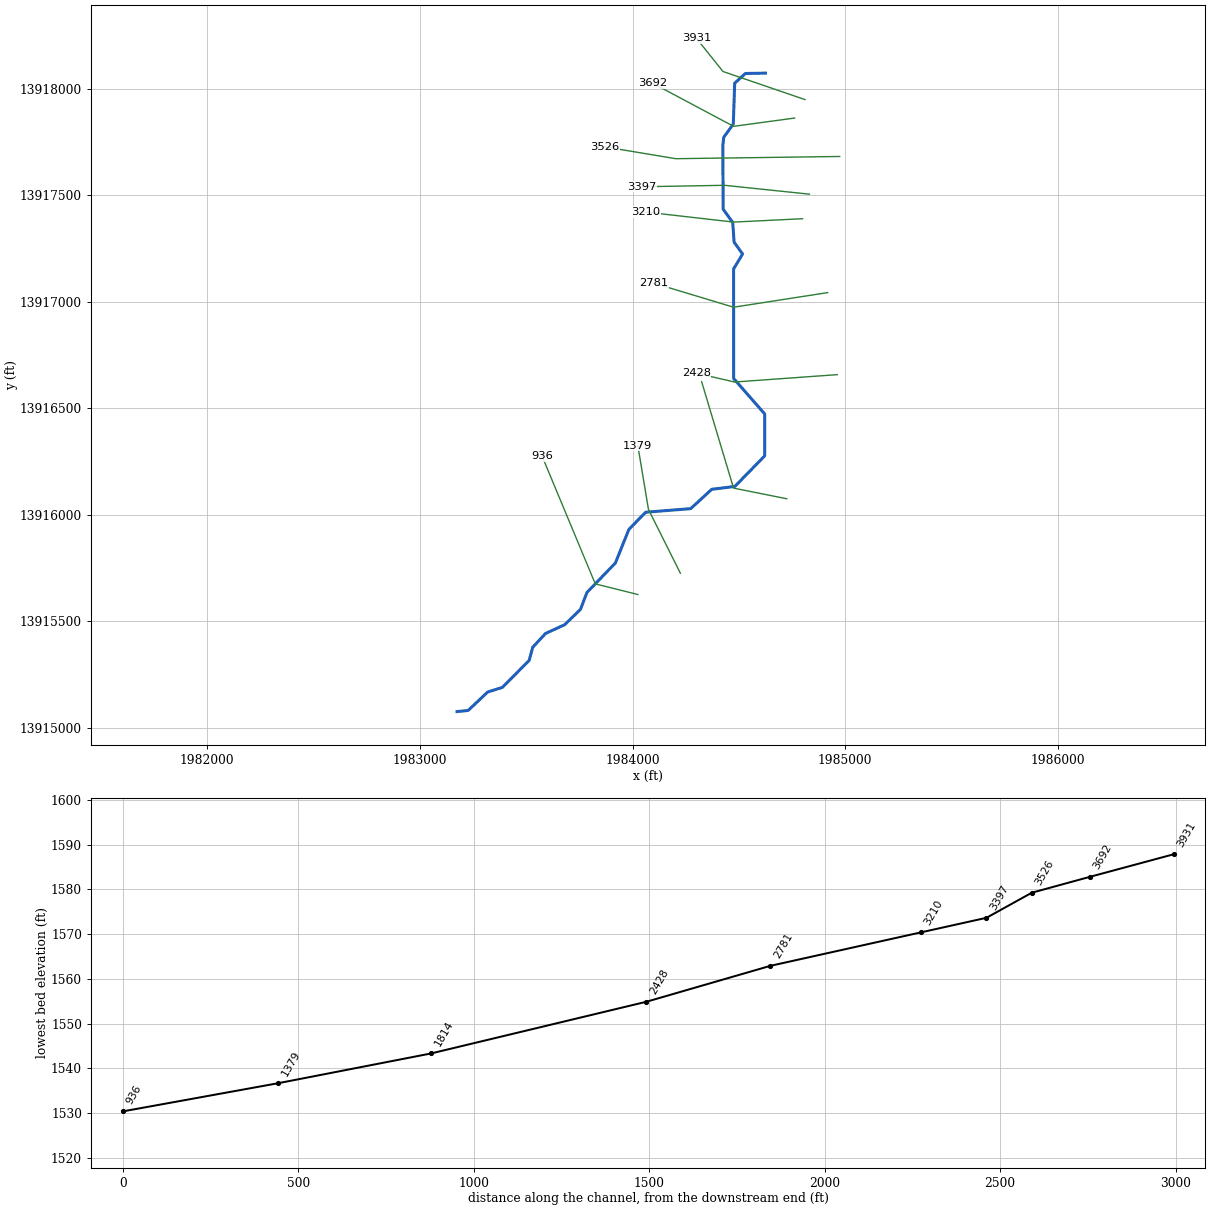
--- Stream0068.prj (project) ---

Proj Title=Stream0068 Base Level Engineering
Current Plan=p01
Default Exp/Contr=0.3,0.1
English Units
Geom File=g01
Flow File=f01
Plan File=p01
BEGIN DESCRIPTION:
Stream0068
END DESCRIPTION:

--- Stream0068.p01 (plan) ---

Plan Title=Multiple Run
Short Identifier=Multiple
Geom File=g01
Flow File=f01
Subcritical Flow
K Sum by GR= 0
Std Step Tol= 0.01
Critical Tol= 0.01
Num of Std Step Trials= 20
Max Error Tol= 0.3
Flow Tol Ratio= 0.001
Split Flow NTrial= 30
Split Flow Tol= 0.02
Split Flow Ratio= 0.02
Log Output Level= 0
Friction Slope Method= 1
Unsteady Friction Slope Method= 2
Unsteady Bridges Friction Slope Method= 1
Parabolic Critical Depth
Global Vel Dist=  1 , 1 , 1
Global Log Level= 0
CheckData=True
Encroach Param= -1, 0, 0, 0
BEGIN DESCRIPTION:
Multiple Run
END DESCRIPTION:

--- Stream0068.f01 (steady flow) ---

Flow Title=Multiple
Number of Profiles=7
Profile Names=10-year,25-year,50-year,1pct_min,100-year,1pct_plu,500-year
River Rch & RM= Stream0068,Reach-1,3931
     564     937    1285     858    1712    3416    3007
Boundary for River Rch & Prof#=Stream0068,Reach-1,1
Up Type=0
Dn Type=3
Dn Slope=0.005
Boundary for River Rch & Prof#=Stream0068,Reach-1,2
Up Type=0
Dn Type=3
Dn Slope=0.005
Boundary for River Rch & Prof#=Stream0068,Reach-1,3
Up Type=0
Dn Type=3
Dn Slope=0.005
Boundary for River Rch & Prof#=Stream0068,Reach-1,4
Up Type=0
Dn Type=3
Dn Slope=0.005
Boundary for River Rch & Prof#=Stream0068,Reach-1,5
Up Type=0
Dn Type=3
Dn Slope=0.005
Boundary for River Rch & Prof#=Stream0068,Reach-1,6
Up Type=0
Dn Type=3
Dn Slope=0.005
Boundary for River Rch & Prof#=Stream0068,Reach-1,7
Up Type=0
Dn Type=3
Dn Slope=0.005

--- Stream0068.g01 (geometry) ---

Geom Title=Existing Conditions

River Reach=Stream0068,Reach-1
Reach XY= 30
      1984625.00     13918075.00      1984530.52     13918073.24
      1984480.32     13918027.73      1984473.78     13917835.51
      1984428.78     13917773.43      1984424.55     13917735.19
      1984426.22     13917435.50      1984471.15     13917373.40
      1984477.55     13917280.89      1984517.44     13917225.00
      1984475.18     13917155.02      1984475.38     13916640.16
      1984621.46     13916473.54      1984621.47     13916276.46
      1984481.17     13916132.86      1984372.58     13916119.46
      1984273.53     13916028.55      1984061.66     13916011.64
      1983983.13     13915931.07      1983919.17     13915772.70
      1983785.78     13915634.68      1983755.23     13915554.87
      1983681.06     13915483.15      1983591.42     13915442.08
      1983530.85     13915377.30      1983514.22     13915315.32
      1983388.21     13915188.63      1983318.95     13915166.84
      1983227.51     13915080.33      1983175.00     13915075.00

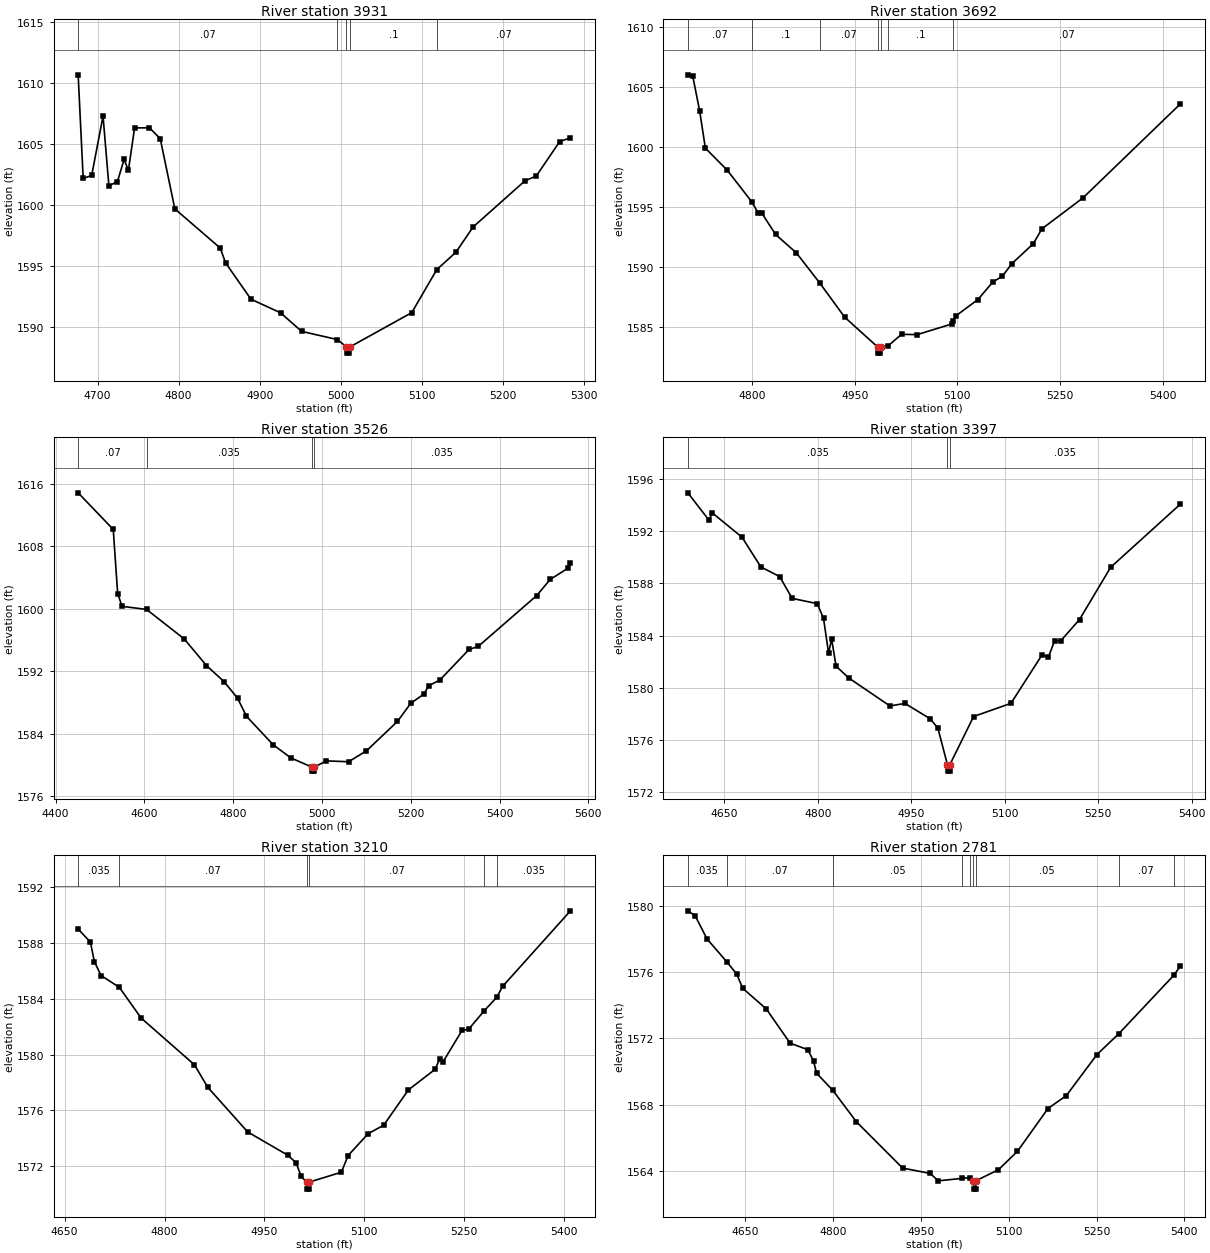
Type RM Length L Ch R = 1,3931,239,239,239
BEGIN DESCRIPTION:
Stream0068 10.0
END DESCRIPTION:
XS GIS Cut Line= 3
      1984810.82     13917950.65      1984425.36     13918082.61
      1984300.37     13918238.85
#Sta/Elev= 30
  4676.0 1610.64  4682.2 1602.15  4692.7 1602.40  4706.7 1607.26  4713.9 1601.56
  4724.4 1601.88  4732.7 1603.71  4738.0 1602.81  4745.6 1606.29  4764.0 1606.30
  4777.3 1605.41  4795.3 1599.66  4851.3 1596.45  4857.9 1595.24  4889.2 1592.26
  4925.8 1591.14  4951.8 1589.62  4996.0 1588.95  5007.1 1588.34  5007.3 1587.84
  5010.8 1587.84  5011.1 1588.34  5087.7 1591.16  5118.6 1594.69  5142.1 1596.10
  5163.3 1598.17  5227.4 1601.96  5241.3 1602.35  5270.1 1605.16  5283.5 1605.49
#Mann=5,-1,0
  4676.0    0.07       0  4996.0     0.1       0  5007.1    0.05       0
  5011.1     0.1       0  5118.6    0.07       0
Bank Sta=5007.1,5011.1
Exp/Cntr=0.3,0.1

Type RM Length L Ch R = 1,3692,166,166,166
BEGIN DESCRIPTION:
Stream0068 7.0
END DESCRIPTION:
XS GIS Cut Line= 3
      1984762.15     13917863.86      1984475.00     13917825.00
      1984095.50     13918027.05
#Sta/Elev= 30
  4706.1 1605.99  4713.3 1605.87  4723.4 1602.97  4731.7 1599.88  4763.8 1598.03
  4799.9 1595.38  4809.3 1594.43  4814.4 1594.45  4834.4 1592.68  4864.7 1591.15
  4898.9 1588.64  4935.3 1585.79  4983.8 1583.29  4984.0 1582.79  4987.5 1582.79
  4987.8 1583.29  4998.3 1583.37  5018.5 1584.36  5041.2 1584.33  5091.9 1585.22
  5094.3 1585.49  5097.8 1585.89  5130.2 1587.26  5152.1 1588.73  5165.8 1589.19
  5179.8 1590.25  5211.1 1591.91  5223.7 1593.15  5283.9 1595.74  5425.8 1603.55
#Mann=7,-1,0
  4706.1    0.07       0  4799.9     0.1       0  4898.9    0.07       0
  4983.8    0.05       0  4987.8    0.07       0  4998.3     0.1       0
  5094.3    0.07       0
Bank Sta=4983.8,4987.8
Exp/Cntr=0.3,0.1

Type RM Length L Ch R = 1,3526,129,129,129
BEGIN DESCRIPTION:
Stream0068 8.0
END DESCRIPTION:
XS GIS Cut Line= 3
      1984973.97     13917683.31      1984203.14     13917672.89
      1983869.94     13917728.42
#Sta/Elev= 30
  4450.9 1614.82  4529.9 1610.14  4539.9 1601.92  4549.9 1600.30  4604.9 1599.91
  4689.9 1596.13  4739.9 1592.73  4779.9 1590.65  4809.9 1588.56  4829.9 1586.25
  4889.9 1582.61  4929.9 1580.92  4977.9 1579.73  4978.2 1579.23  4981.7 1579.23
  4981.9 1579.73  5009.9 1580.54  5059.9 1580.43  5099.9 1581.81  5169.9 1585.58
  5199.9 1587.90  5230.1 1589.11  5240.2 1590.15  5265.3 1590.87  5331.4 1594.80
  5351.7 1595.17  5483.5 1601.68  5513.9 1603.74  5554.5 1605.20  5559.6 1605.85
#Mann=4,-1,0
  4450.9    0.07       0  4604.9   0.035       0  4977.9   0.035       0
  4981.9   0.035       0
Bank Sta=4977.9,4981.9
Exp/Cntr=0.3,0.1

Type RM Length L Ch R = 1,3397,187,187,187
BEGIN DESCRIPTION:
Stream0068 9.0
END DESCRIPTION:
XS GIS Cut Line= 3
      1984831.58     13917506.23      1984432.30     13917547.89
      1984043.41     13917540.95
#Sta/Elev= 30
  4591.2 1594.93  4625.2 1592.83  4630.3 1593.40  4678.2 1591.53  4708.4 1589.26
  4738.6 1588.52  4758.7 1586.85  4798.9 1586.45  4809.0 1585.33  4817.1 1582.68
  4822.1 1583.73  4829.1 1581.67  4849.2 1580.77  4915.6 1578.62  4939.7 1578.81
  4979.9 1577.65  4992.6 1576.93  5007.9 1574.13  5008.2 1573.63  5011.7 1573.63
  5011.9 1574.13  5050.0 1577.81  5110.0 1578.82  5160.0 1582.54  5170.0 1582.34
  5180.0 1583.61  5190.0 1583.61  5220.0 1585.23  5270.0 1589.23  5381.6 1594.05
#Mann=3,-1,0
  4591.2   0.035       0  5007.9   0.035       0  5011.9   0.035       0
Bank Sta=5007.9,5011.9
Exp/Cntr=0.3,0.1

Type RM Length L Ch R = 1,3210,429,429,429
BEGIN DESCRIPTION:
Stream0068 6.0
END DESCRIPTION:
XS GIS Cut Line= 3
      1984799.35     13917390.84      1984475.00     13917375.00
      1984063.22     13917422.10
#Sta/Elev= 30
  4670.3 1588.98  4688.6 1588.06  4694.7 1586.65  4704.7 1585.66  4732.2 1584.81
  4764.8 1582.62  4844.9 1579.27  4864.9 1577.66  4924.9 1574.46  4985.0 1572.80
  4997.5 1572.26  5005.1 1571.29  5013.2 1570.87  5013.4 1570.37  5016.9 1570.37
  5017.2 1570.87  5065.5 1571.58  5075.6 1572.77  5105.7 1574.34  5129.0 1574.94
  5166.1 1577.47  5206.4 1578.95  5213.2 1579.70  5218.3 1579.49  5246.7 1581.73
  5256.7 1581.82  5279.9 1583.13  5298.8 1584.10  5307.6 1584.88  5409.5 1590.29
#Mann=6,-1,0
  4670.3   0.035       0  4732.2    0.07       0  5013.2    0.05       0
  5017.2    0.07       0  5279.9    0.05       0  5298.8   0.035       0
Bank Sta=5013.2,5017.2
Exp/Cntr=0.3,0.1

Type RM Length L Ch R = 1,2781,353,353,353
BEGIN DESCRIPTION:
Stream0068 5.0
END DESCRIPTION:
XS GIS Cut Line= 3
      1984917.39     13917043.62      1984475.00     13916975.00
      1984099.02     13917088.44
#Sta/Elev= 30
  4552.3 1579.70  4564.8 1579.40  4585.1 1578.00  4618.6 1576.63  4635.7 1575.88
  4646.0 1575.02  4686.3 1573.77  4726.8 1571.71  4757.1 1571.31  4766.9 1570.63
  4772.0 1569.89  4799.7 1568.86  4840.0 1566.96  4919.0 1564.16  4966.0 1563.84
  4979.7 1563.39  5020.4 1563.54  5033.5 1563.58  5039.8 1563.39  5040.0 1562.89
  5043.5 1562.89  5043.8 1563.39  5082.4 1564.06  5114.9 1565.17  5167.1 1567.76
  5198.4 1568.54  5250.7 1571.02  5287.8 1572.27  5381.7 1575.80  5392.7 1576.35
#Mann=9,-1,0
  4552.3   0.035       0  4618.6    0.07       0  4799.7    0.05       0
  5020.4    0.07       0  5033.5    0.05       0  5039.8    0.05       0
  5043.8    0.05       0  5287.8    0.07       0  5381.7    0.05       0
Bank Sta=5039.8,5043.8
Exp/Cntr=0.3,0.1

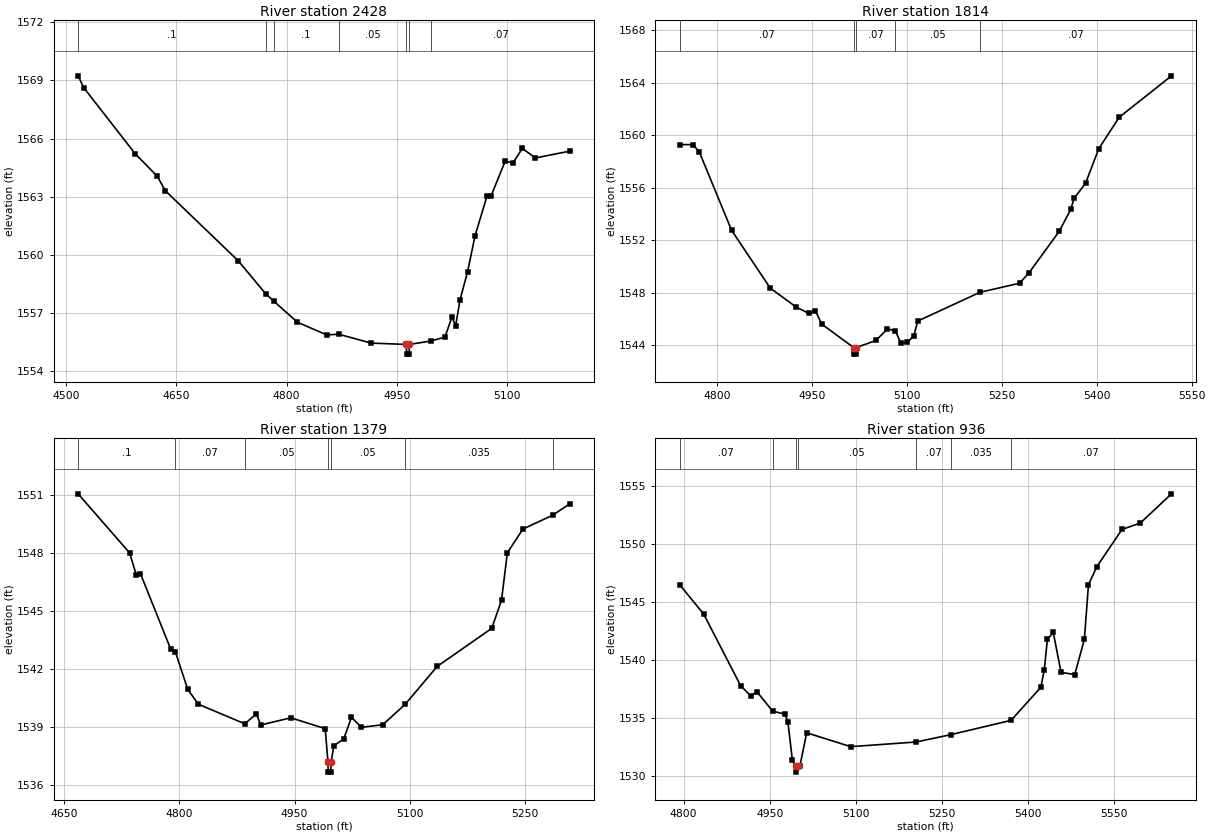
Type RM Length L Ch R = 1,2428,614,614,614
BEGIN DESCRIPTION:
Stream0068 4.0
END DESCRIPTION:
XS GIS Cut Line= 3
      1984962.55     13916658.21      1984479.90     13916623.48
      1984299.64     13916665.08
#Sta/Elev= 30
  4516.2 1569.24  4523.8 1568.63  4594.0 1565.21  4624.0 1564.05  4634.8 1563.31
  4734.3 1559.68  4771.8 1557.97  4782.3 1557.61  4814.5 1556.52  4854.6 1555.86
  4870.6 1555.90  4914.8 1555.44  4962.9 1555.37  4963.2 1554.87  4966.7 1554.87
  4966.9 1555.37  4996.5 1555.55  5015.4 1555.75  5024.8 1556.78  5029.9 1556.34
  5035.9 1557.67  5046.2 1559.13  5056.4 1560.99  5072.7 1563.05  5077.8 1563.01
  5097.5 1564.85  5107.8 1564.73  5120.6 1565.49  5138.5 1565.00  5185.1 1565.35
#Mann=7,-1,0
  4516.2     0.1       0  4771.8    0.07       0  4782.3     0.1       0
  4870.6    0.05       0  4962.9    0.05       0  4966.9    0.05       0
  4996.5    0.07       0
Bank Sta=4962.9,4966.9
Exp/Cntr=0.3,0.1

Type RM Length L Ch R = 1,1814,435,435,435
BEGIN DESCRIPTION:
Stream0068 3.0
END DESCRIPTION:
XS GIS Cut Line= 3
      1984724.99     13916075.00      1984475.00     13916125.00
      1984324.99     13916625.04
#Sta/Elev= 30
  4741.1 1559.27  4761.5 1559.27  4771.7 1558.72  4822.7 1552.75  4883.9 1548.34
  4924.7 1546.90  4945.1 1546.41  4955.3 1546.60  4965.4 1545.59  5015.8 1543.81
  5016.0 1543.31  5019.5 1543.31  5019.8 1543.81  5050.9 1544.35  5069.1 1545.23
  5081.7 1545.09  5090.0 1544.17  5100.4 1544.21  5110.9 1544.70  5117.0 1545.83
  5215.4 1548.02  5277.9 1548.71  5292.7 1549.49  5340.6 1552.66  5358.8 1554.33
  5364.1 1555.17  5382.3 1556.33  5403.2 1558.96  5435.4 1561.35  5518.1 1564.51
#Mann=5,-1,0
  4741.1    0.07       0  5015.8    0.05       0  5019.8    0.07       0
  5081.7    0.05       0  5215.4    0.07       0
Bank Sta=5015.8,5019.8
Exp/Cntr=0.3,0.1

Type RM Length L Ch R = 1,1379,443,443,443
BEGIN DESCRIPTION:
Stream0068 2.0
END DESCRIPTION:
XS GIS Cut Line= 3
      1984225.02     13915724.97      1984075.00     13916025.00
      1984025.00     13916325.01
#Sta/Elev= 30
  4668.4 1551.07  4735.5 1548.01  4743.9 1546.89  4749.5 1546.94  4788.6 1543.06
  4795.0 1542.89  4811.0 1540.95  4825.0 1540.18  4885.3 1539.17  4900.4 1539.69
  4906.0 1539.11  4945.2 1539.48  4989.9 1538.92  4993.5 1537.17  4993.7 1536.67
  4997.2 1536.67  4997.5 1537.17  5001.1 1538.03  5014.0 1538.39  5024.1 1539.51
  5036.8 1538.99  5064.7 1539.12  5094.2 1540.19  5135.6 1542.14  5206.6 1544.11
  5219.3 1545.57  5226.9 1548.02  5247.2 1549.25  5285.7 1549.96  5308.0 1550.55
#Mann=7,-1,0
  4668.4     0.1       0  4795.0    0.07       0  4885.3    0.05       0
  4993.5    0.05       0  4997.5    0.05       0  5094.2   0.035       0
  5285.7    0.05       0
Bank Sta=4993.5,4997.5
Exp/Cntr=0.3,0.1

Type RM Length L Ch R = 1,936,0,0,0
BEGIN DESCRIPTION:
Stream0068 1.0
END DESCRIPTION:
XS GIS Cut Line= 3
      1984025.02     13915624.99      1983825.00     13915675.00
      1983574.99     13916275.02
#Sta/Elev= 30
  4793.6 1546.46  4834.9 1543.97  4899.3 1537.81  4917.3 1536.91  4927.6 1537.29
  4955.2 1535.61  4976.6 1535.36  4981.7 1534.68  4989.5 1531.41  4995.2 1530.87
  4995.4 1530.37  4999.2 1530.87  5002.5 1530.87  5014.4 1533.75  5091.3 1532.56
  5204.9 1532.96  5265.2 1533.59  5370.4 1534.82  5422.3 1537.67  5428.2 1539.17
  5433.7 1541.78  5443.9 1542.38  5457.5 1538.95  5481.3 1538.76  5498.1 1541.79
  5505.2 1546.48  5519.8 1548.04  5563.7 1551.24  5595.6 1551.79  5649.8 1554.30
#Mann=7,-1,0
  4793.6    0.07       0  4955.2    0.05       0  4995.2    0.05       0
  4999.2    0.05       0  5204.9    0.07       0  5265.2   0.035       0
  5370.4    0.07       0
Bank Sta=4995.2,4999.2
Exp/Cntr=0.3,0.1

Chan Stop Cuts=-1