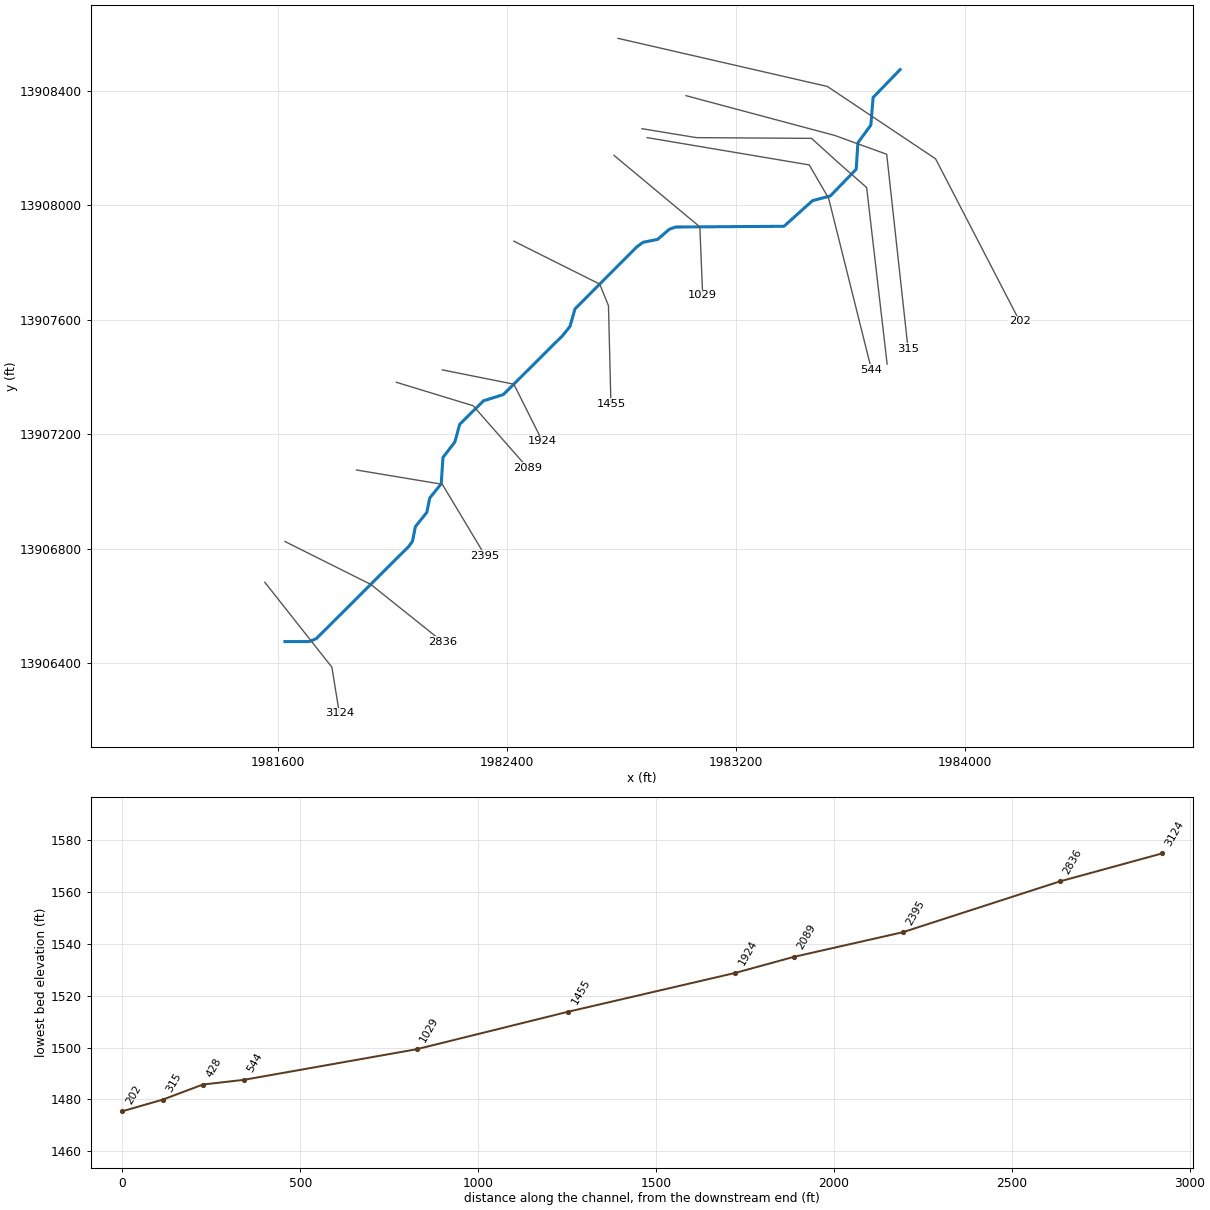
--- Stream0069.prj (project) ---

Proj Title=Stream0069 Base Level Engineering
Current Plan=p01
Default Exp/Contr=0.3,0.1
English Units
Geom File=g01
Flow File=f01
Plan File=p01
Y Axis Title=Elevation
X Axis Title(PF)=Main Channel Distance
X Axis Title(XS)=Station
BEGIN DESCRIPTION:
Stream0069
END DESCRIPTION:
DSS Export Rating Curves= 0
DSS Export Rating Curve Sorted= 0
DSS Export Volume Flow Curves= 0
DXF OffsetX= 0
DXF OffsetY= 0
DXF ScaleX= 1
DXF ScaleY= 10

--- Stream0069.p01 (plan) ---

Plan Title=Multiple Run
Short Identifier=Multiple
Geom File=g01
Flow File=f01
Subcritical Flow
K Sum by GR= 0
Std Step Tol= 0.01
Critical Tol= 0.01
Num of Std Step Trials= 20
Max Error Tol= 0.3
Flow Tol Ratio= 0.001
Split Flow NTrial= 30
Split Flow Tol= 0.02
Split Flow Ratio= 0.02
Log Output Level= 0
Friction Slope Method= 1
Unsteady Friction Slope Method= 2
Unsteady Bridges Friction Slope Method= 1
Parabolic Critical Depth
Global Vel Dist=  1 , 1 , 1
Global Log Level= 0
CheckData=True
Encroach Param= -1, 0, 0, 0
BEGIN DESCRIPTION:
Multiple Run
END DESCRIPTION:

--- Stream0069.f01 (steady flow) ---

Flow Title=Multiple
Number of Profiles=7
Profile Names=10-year,25-year,50-year,1pct_min,100-year,1pct_plu,500-year
River Rch & RM= Stream0069,Reach-1,3124
     338     536     714     464     926    1847    1532
Boundary for River Rch & Prof#=Stream0069,Reach-1,1
Up Type=0
Dn Type=3
Dn Slope=0.005
Boundary for River Rch & Prof#=Stream0069,Reach-1,2
Up Type=0
Dn Type=3
Dn Slope=0.005
Boundary for River Rch & Prof#=Stream0069,Reach-1,3
Up Type=0
Dn Type=3
Dn Slope=0.005
Boundary for River Rch & Prof#=Stream0069,Reach-1,4
Up Type=0
Dn Type=3
Dn Slope=0.005
Boundary for River Rch & Prof#=Stream0069,Reach-1,5
Up Type=0
Dn Type=3
Dn Slope=0.005
Boundary for River Rch & Prof#=Stream0069,Reach-1,6
Up Type=0
Dn Type=3
Dn Slope=0.005
Boundary for River Rch & Prof#=Stream0069,Reach-1,7
Up Type=0
Dn Type=3
Dn Slope=0.005

--- Stream0069.g01 (geometry) ---

Geom Title=Existing Conditions
Program Version=4.10

River Reach=Stream0069      ,Reach-1
Reach XY= 30
        1981625.       13906475.      1981709.95     13906475.12
      1981734.82     13906485.43      1982058.36     13906808.32
      1982071.05     13906826.63       1982081.1     13906877.19
      1982120.84     13906926.72      1982131.12     13906977.18
      1982171.17     13907026.58      1982177.33     13907119.03
      1982218.86     13907172.83      1982235.75     13907234.71
      1982318.93     13907316.85      1982388.21     13907338.63
      1982595.38     13907544.84      1982621.02     13907576.65
      1982638.63     13907638.21      1982854.91     13907855.22
      1982876.63     13907871.06      1982927.17     13907881.14
      1982968.92     13907916.91      1982990.21     13907924.49
      1983369.14     13907927.06      1983468.96     13908016.82
      1983531.07     13908033.15      1983621.39     13908126.48
      1983627.36     13908219.02      1983672.65     13908280.98
      1983680.46     13908377.45        1983775.       13908475.

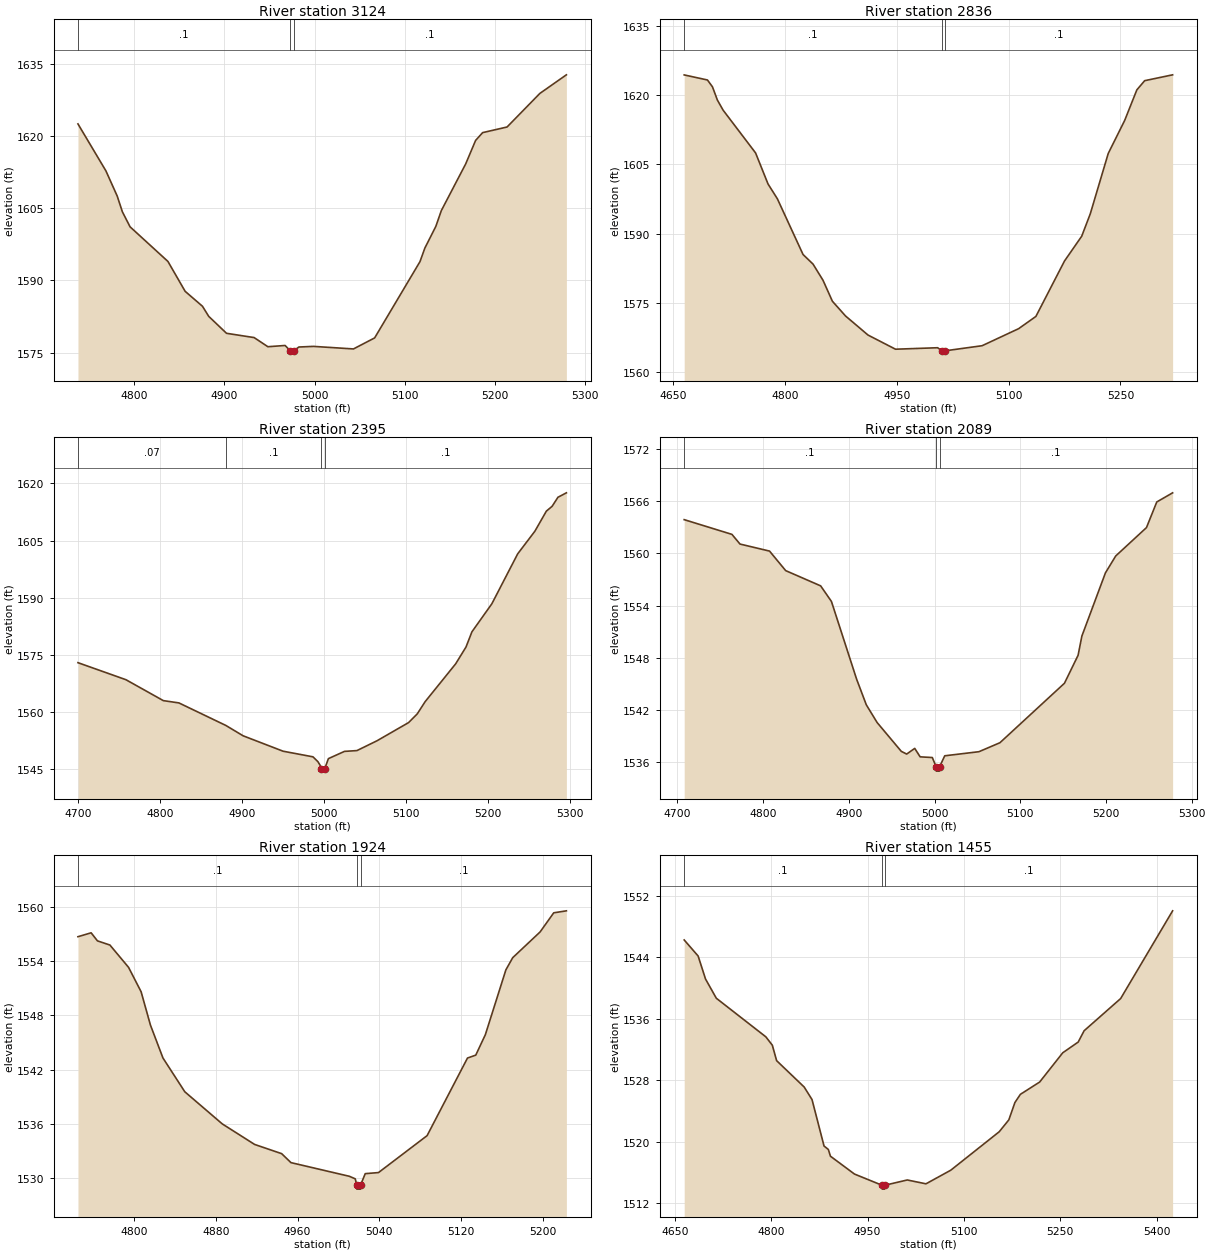
Type RM Length L Ch R = 1 ,3124    ,288,288,288
BEGIN DESCRIPTION:
Stream0069 7.0
END DESCRIPTION:
XS GIS Cut Line= 3
      1981554.75     13906682.38      1981789.15     13906385.47
      1981815.19     13906224.04
#Sta/Elev= 30
  4737.6 1622.51  4768.6 1612.76  4781.1 1607.54  4786.9 1604.24  4795.4 1601.13
  4837.4 1593.94  4856.5 1587.73  4875.7 1584.63  4882.7 1582.52  4902.4 1579.01
    4933 1578.12  4948.3 1576.22  4967.4 1576.48    4973 1575.39  4973.3 1574.89
    4977 1575.39  4982.7 1576.16  4998.9 1576.29  5043.2 1575.76  5066.7 1578.05
    5117  1593.9  5122.4 1596.71  5134.6 1601.23  5140.7 1604.51  5167.7  1614.2
  5178.7 1619.08  5186.5  1620.7  5213.6 1621.87    5250 1628.85  5279.4 1632.71
#Mann= 3 ,-1 , 0
  4737.6      .1       0    4973     .05       0    4977      .1       0
Bank Sta=4973,4977
XS Rating Curve= 0 ,0
Exp/Cntr=0.3,0.1

Type RM Length L Ch R = 1 ,2836    ,441,441,441
BEGIN DESCRIPTION:
Stream0069 6.0
END DESCRIPTION:
XS GIS Cut Line= 3
      1981625.03     13906824.98        1981925.       13906675.
      1982174.98     13906475.02
#Sta/Elev= 30
  4664.6 1624.41  4695.8 1623.31  4702.5 1621.84  4709.2 1618.94  4716.8 1616.77
  4760.4 1607.49  4777.1 1600.76  4789.7 1597.53  4824.1 1585.46  4837.5 1583.38
  4850.9 1579.87  4863.5 1575.32  4881.1 1572.13  4911.3 1567.99  4948.2 1564.92
  5004.7 1565.24  5010.7 1564.57    5011 1564.07  5014.7 1564.57  5064.5 1565.68
  5113.5 1569.38  5136.6 1572.03    5175 1584.05  5198.1 1589.43  5209.6 1594.29
  5233.7 1607.38  5255.7 1614.52  5272.1 1621.17  5282.6 1623.16  5320.1 1624.43
#Mann= 3 ,-1 , 0
  4664.6      .1       0  5010.7     .05       0  5014.7      .1       0
Bank Sta=5010.7,5014.7
XS Rating Curve= 0 ,0
Exp/Cntr=0.3,0.1

Type RM Length L Ch R = 1 ,2395    ,306,306,306
BEGIN DESCRIPTION:
Stream0069 5.0
END DESCRIPTION:
XS GIS Cut Line= 3
      1981875.02       13907075.        1982175.       13907025.
      1982324.97     13906775.06
#Sta/Elev= 30
  4700.2 1572.95  4758.7 1568.48  4804.3 1562.99  4823.3 1562.39  4880.6 1556.47
  4901.6 1553.76  4950.3 1549.72  4986.8 1548.24  4992.8 1546.97  4996.7  1545.6
  4996.9 1544.99  4997.2 1544.49  5000.9 1544.99  5005.6 1547.77  5025.2 1549.67
  5040.4 1549.88  5064.9 1552.46  5103.4 1557.23  5113.9  1559.5  5123.6 1562.73
  5160.8 1572.65  5173.4 1577.06  5180.6 1581.04  5204.9  1588.4  5236.4  1601.5
  5257.4 1607.45  5271.4 1612.72  5278.4 1613.98  5285.5 1616.35  5295.8 1617.52
#Mann= 4 ,-1 , 0
  4700.2     .07       0  4880.6      .1       0  4996.9     .05       0
  5000.9      .1       0
Bank Sta=4996.9,5000.9
XS Rating Curve= 0 ,0
Exp/Cntr=0.3,0.1

Type RM Length L Ch R = 1 ,2089    ,165,165,165
BEGIN DESCRIPTION:
Mapping XS ce88220c
END DESCRIPTION:
XS GIS Cut Line= 3
      1982014.42     13907381.62      1982282.67     13907299.67
      1982473.54     13907082.12
#Sta/Elev= 30
  4707.9 1563.86  4763.6 1562.17    4773 1561.06  4807.5 1560.25  4826.3 1558.01
  4867.1 1556.26  4879.7 1554.47  4909.1 1545.54  4920.4  1542.6    4933 1540.57
  4961.2 1537.26  4967.5 1536.95  4976.9  1537.6  4983.2 1536.63  4997.4 1536.55
  5001.9 1535.49  5002.1 1534.99  5005.6 1534.99  5005.9 1535.49  5011.9 1536.75
  5051.8 1537.22  5076.3 1538.25  5151.6 1545.08  5167.5 1548.29  5171.9 1550.49
  5199.4 1557.75  5211.4 1559.69  5247.3 1562.95  5259.3 1565.89  5277.8 1566.94
#Mann= 3 ,-1 , 0
  4707.9      .1       0  5001.9     .05       0  5005.9      .1       0
Bank Sta=5001.9,5005.9
XS Rating Curve= 0 ,0
Exp/Cntr=0.3,0.1

Type RM Length L Ch R = 1 ,1924    ,469,469,469
BEGIN DESCRIPTION:
Stream0069 4.0
END DESCRIPTION:
XS GIS Cut Line= 3
        1982175.       13907425.        1982425.       13907375.
      1982525.02     13907174.96
#Sta/Elev= 30
  4744.8 1556.69  4757.7 1557.12  4763.9 1556.23  4776.1 1555.77  4794.4  1553.3
  4806.7  1550.6  4815.8 1546.93  4828.1 1543.28  4849.5 1539.55  4886.2    1536
  4917.9 1533.73  4944.4 1532.71  4953.5 1531.72  5010.7 1530.21  5016.5 1529.93
  5017.9 1529.29  5018.1 1528.79  5021.6 1528.79  5021.9 1529.29  5026.3  1530.5
  5039.3 1530.62  5086.9  1534.7  5126.5 1543.28  5134.6  1543.6    5144 1545.86
  5164.1 1553.02  5170.8 1554.37  5197.6 1557.21    5211 1559.33  5223.4 1559.55
#Mann= 3 ,-1 , 0
  4744.8      .1       0  5017.9     .05       0  5021.9      .1       0
Bank Sta=5017.9,5021.9
XS Rating Curve= 0 ,0
Exp/Cntr=0.3,0.1

Type RM Length L Ch R = 1 ,1455    ,426,426,426
BEGIN DESCRIPTION:
Stream0069 3.0
END DESCRIPTION:
XS GIS Cut Line= 4
      1982424.99       13907875.        1982725.       13907725.
       1982755.7     13907649.37      1982764.25     13907306.12
#Sta/Elev= 30
  4664.6 1546.25  4686.3 1544.16  4697.8 1541.17  4714.6 1538.67  4791.7 1533.65
  4801.8 1532.56  4808.5 1530.55  4851.4 1527.12  4863.6 1525.49  4882.3 1519.45
    4889    1519  4892.3 1518.12  4929.7  1515.8  4972.7 1514.34    4973 1513.84
  4976.5 1513.84  4976.7 1514.34  5011.9 1515.03    5041 1514.53  5079.6  1516.3
    5155  1521.3    5170 1522.85  5179.5 1525.11    5188 1526.17    5218 1527.77
    5254 1531.58    5278 1532.97  5287.2 1534.44  5344.1 1538.63    5425 1550.04
#Mann= 3 ,-1 , 0
  4664.6      .1       0  4972.7     .05       0  4976.7      .1       0
Bank Sta=4972.7,4976.7
XS Rating Curve= 0 ,0
Exp/Cntr=0.3,0.1

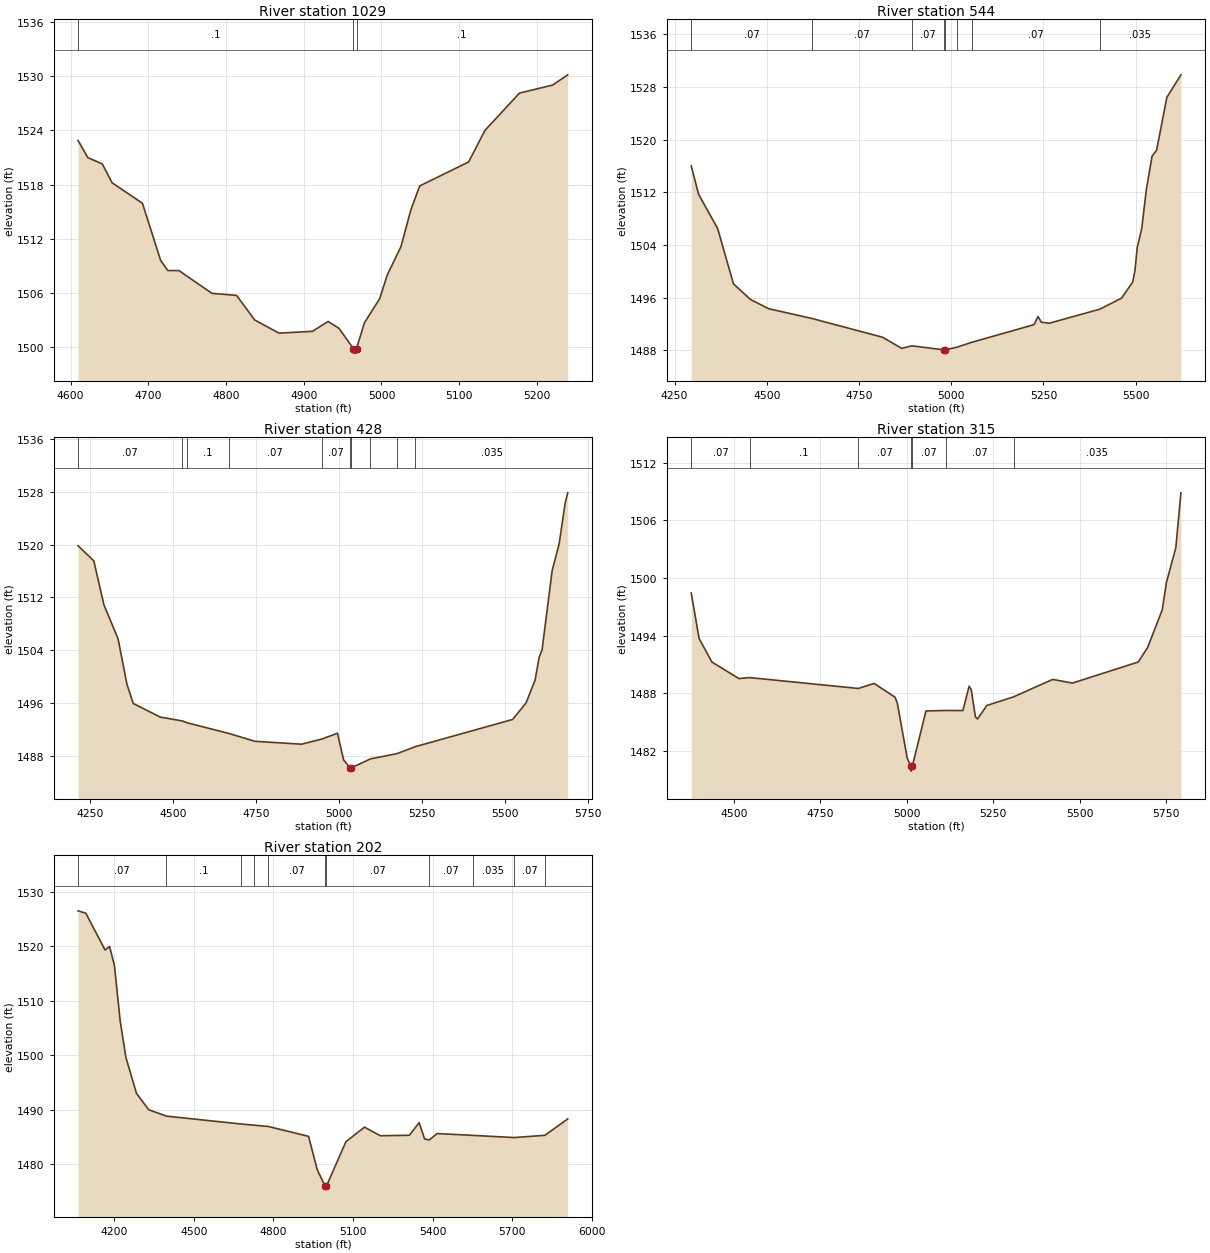
Type RM Length L Ch R = 1 ,1029    ,485,485,485
BEGIN DESCRIPTION:
Stream0069 2.0
END DESCRIPTION:
XS GIS Cut Line= 3
      1982774.98     13908175.01        1983075.       13907925.
      1983084.94     13907685.64
#Sta/Elev= 30
  4609.6 1522.88  4622.2 1520.99  4640.8 1520.29  4653.5  1518.2  4692.5 1515.94
  4715.9 1509.62  4725.2  1508.5  4739.4  1508.5  4781.9 1505.98  4813.6 1505.75
    4837 1503.03  4868.2 1501.58  4911.2 1501.78  4931.4 1502.87  4945.4 1502.11
  4963.9 1499.87  4964.1 1499.37  4967.6 1499.37  4967.9 1499.87  4978.2 1502.74
  4997.8  1505.4  5007.5 1508.01  5025.1 1511.14    5038 1515.25  5049.2 1517.85
  5112.2 1520.51  5133.2    1524  5177.6 1528.12  5220.3 1529.01  5239.7 1530.14
#Mann= 3 ,-1 , 0
  4609.6      .1       0  4963.9     .05       0  4967.9      .1       0
Bank Sta=4963.9,4967.9
XS Rating Curve= 0 ,0
Exp/Cntr=0.3,0.1

Type RM Length L Ch R = 1 ,544     ,116,116,116
BEGIN DESCRIPTION:
Stream0069 1.0
END DESCRIPTION:
XS GIS Cut Line= 4
      1982890.94     13908237.04      1983457.29     13908141.61
        1983525.       13908025.      1983674.99     13907425.04
#Sta/Elev= 30
  4295.2 1516.04  4315.2 1511.72  4366.9 1506.51  4409.6 1498.12  4455.2 1495.76
  4504.6 1494.34  4622.1 1492.85  4814.2 1489.99  4865.9  1488.3    4893 1488.69
  4979.8 1488.08  4980.1 1487.58  4983.8 1488.08  5015.6 1488.48  5055.5 1489.22
  5224.7 1491.91  5235.3 1493.14  5244.5 1492.27  5266.2 1492.13  5403.2 1494.26
  5461.8 1495.94  5491.9 1498.36  5498.1  1500.1  5504.3 1503.61  5516.7 1506.56
    5529 1512.43  5544.5 1517.49  5556.9 1518.43  5584.7 1526.45  5622.8 1529.87
#Mann= 8 ,-1 , 0
  4295.2     .07       0  4622.1     .07       0    4893     .07       0
  4979.8     .05       0  4983.8     .07       0  5015.6     .07       0
  5055.5     .07       0  5403.2    .035       0
Bank Sta=4979.8,4983.8
XS Rating Curve= 0 ,0
Exp/Cntr=0.3,0.1

Type RM Length L Ch R = 1 ,428     ,113,113,113
BEGIN DESCRIPTION:
Stream0069 1.1
END DESCRIPTION:
XS GIS Cut Line= 6
      1982872.71     13908268.28      1983062.86     13908237.03
      1983465.21     13908234.42      1983561.56     13908147.18
      1983657.91     13908062.55      1983729.53     13907445.37
#Sta/Elev= 30
    4214 1519.83  4261.6 1517.53    4292 1510.89  4334.6 1505.75  4361.3 1498.89
  4380.2 1495.98  4461.5 1493.92  4528.5 1493.33  4542.1 1493.07  4668.3 1491.44
  4746.5 1490.26  4887.1 1489.82  4947.6 1490.59  4995.3 1491.48  5013.5 1487.47
    5033 1486.25  5033.3 1485.75    5037 1486.25  5094.4  1487.6  5174.2 1488.39
  5229.8 1489.45  5522.6 1493.56  5563.1 1496.06  5590.3 1499.51  5602.4 1502.95
  5611.4 1504.11  5641.6 1516.05  5662.8 1520.13  5680.9  1526.3  5688.6 1527.82
#Mann= 10 ,-1 , 0
    4214     .07       0  4528.5    .035       0  4542.1      .1       0
  4668.3     .07       0  4947.6     .07       0    5033     .05       0
    5037     .07       0  5094.4     .07       0  5174.2     .07       0
  5229.8    .035       0
Bank Sta=5033,5037
XS Rating Curve= 0 ,0
Exp/Cntr=0.3,0.1

Type RM Length L Ch R = 1 ,315     ,113,113,113
BEGIN DESCRIPTION:
Mapping XS 822e46c0
END DESCRIPTION:
XS GIS Cut Line= 4
      1983026.68     13908383.72      1983545.75     13908244.84
      1983728.04     13908178.87      1983802.69     13907498.34
#Sta/Elev= 30
  4376.7 1498.44  4399.5 1493.71  4436.5 1491.26  4514.4 1489.54  4545.4 1489.64
  4859.6 1488.51  4905.7 1489.03  4966.1  1487.6  4972.4 1487.01  5001.2 1481.26
  5011.9 1480.41  5012.2 1479.91  5015.9 1480.41  5055.4 1486.17  5112.5 1486.22
  5162.1 1486.21  5180.2 1488.74  5186.2  1488.4  5198.3 1485.57  5204.3 1485.33
  5231.5 1486.74    5309 1487.64  5421.6 1489.45    5479 1489.07  5669.1 1491.26
  5696.2 1492.77  5738.5 1496.68  5750.6 1499.54  5777.7 1503.14  5792.5 1508.86
#Mann= 7 ,-1 , 0
  4376.7     .07       0  4545.4      .1       0  4859.6     .07       0
  5011.9     .05       0  5015.9     .07       0  5112.5     .07       0
    5309    .035       0
Bank Sta=5011.9,5015.9
XS Rating Curve= 0 ,0
Exp/Cntr=0.3,0.1

Type RM Length L Ch R = 1 ,202     ,0,0,0
BEGIN DESCRIPTION:
Stream0069 0.0
END DESCRIPTION:
XS GIS Cut Line= 4
      1982788.99     13908584.19      1983520.54       13908416.
      1983898.83     13908162.92      1984192.79     13907594.73
#Sta/Elev= 30
  4063.4 1526.51  4092.8 1526.07  4165.4 1519.32  4182.1 1519.99  4200.6 1516.49
  4222.1 1506.38  4243.7 1499.64  4283.7 1493.02  4329.9 1490.02  4396.7 1488.85
  4678.8  1487.4  4726.8 1487.19  4780.7 1486.95  4932.1 1485.14  4965.1 1478.99
  4995.1 1475.96  4995.3 1475.46  4999.1 1475.96  5072.9 1484.15  5143.1 1486.83
  5202.8 1485.25    5312 1485.34    5349 1487.66  5369.3 1484.67  5386.9 1484.47
  5416.8 1485.65  5550.9 1485.32  5706.8 1484.92  5822.8 1485.33  5908.9 1488.34
#Mann= 11 ,-1 , 0
  4063.4     .07       0  4396.7      .1       0  4678.8    .035       0
  4726.8      .1       0  4780.7     .07       0  4995.1     .05       0
  4999.1     .07       0  5386.9     .07       0  5550.9    .035       0
  5706.8     .07       0  5822.8    .035       0
Bank Sta=4995.1,4999.1
XS Rating Curve= 0 ,0
Exp/Cntr=0.3,0.1

Chan Stop Cuts=-1
Use User Specified Reach Order=0
Composite Channel Slope=5