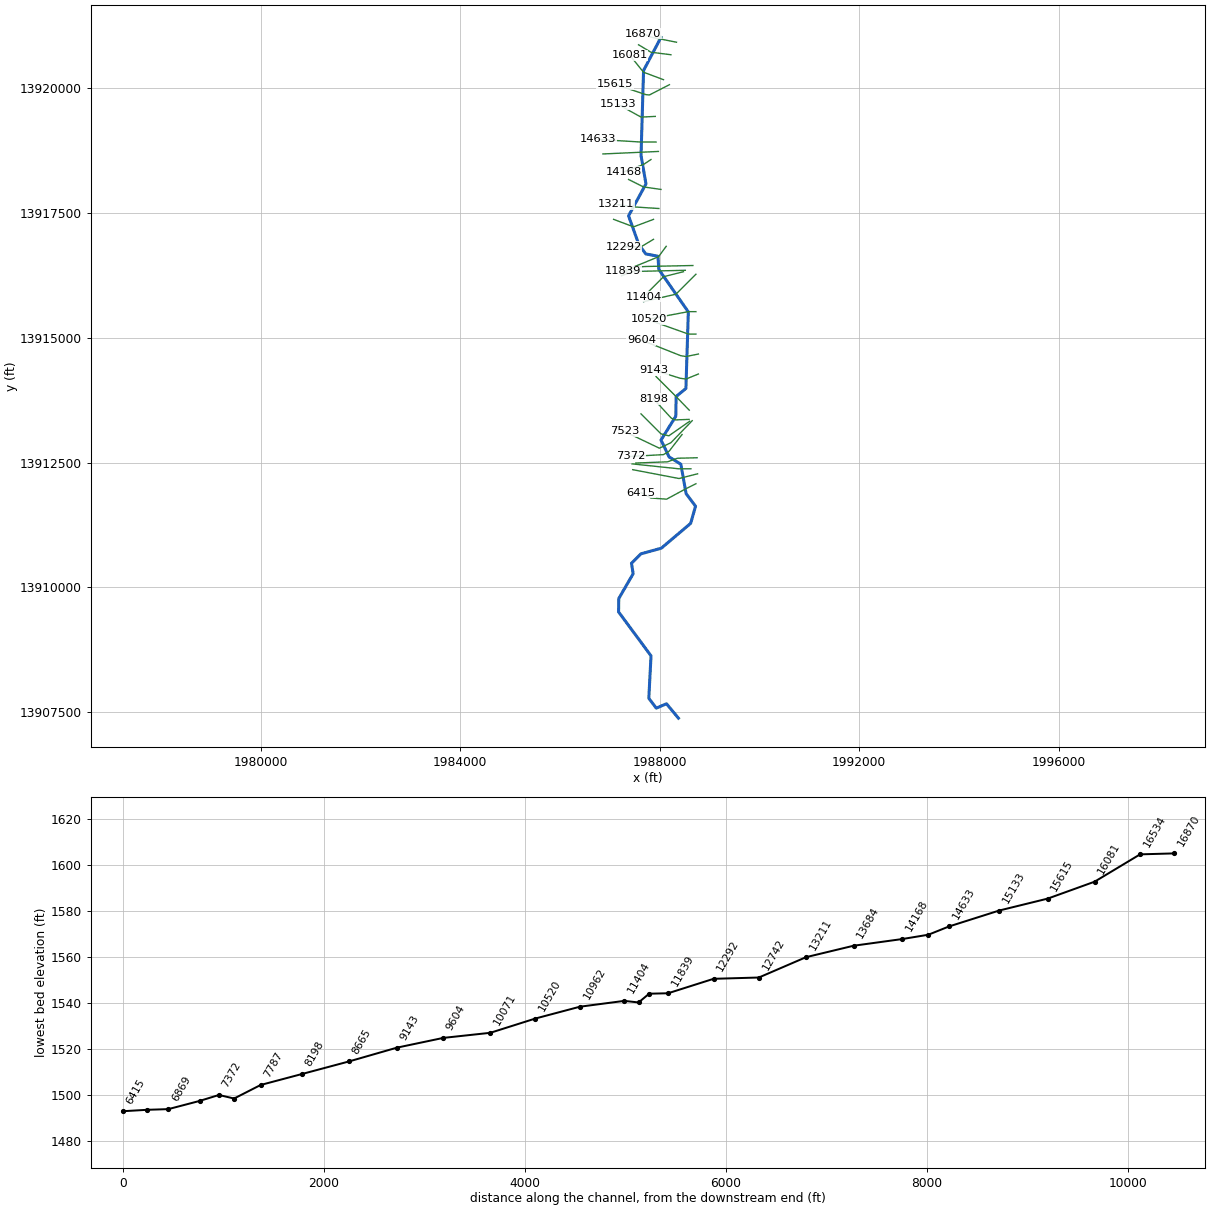
--- Stream0070.prj (project) ---

Proj Title=Stream0070 Base Level Engineering
Current Plan=p01
Default Exp/Contr=0.3,0.1
English Units
Geom File=g01
Flow File=f01
Plan File=p01
Y Axis Title=Elevation
X Axis Title(PF)=Main Channel Distance
X Axis Title(XS)=Station
BEGIN DESCRIPTION:
Stream0070
END DESCRIPTION:
DSS Export Rating Curves= 0
DSS Export Rating Curve Sorted= 0
DSS Export Volume Flow Curves= 0
DXF OffsetX= 0
DXF OffsetY= 0
DXF ScaleX= 1
DXF ScaleY= 10

--- Stream0070.p01 (plan) ---

Plan Title=Multiple Run
Short Identifier=Multiple
Geom File=g01
Flow File=f01
Subcritical Flow
K Sum by GR= 0
Std Step Tol= 0.01
Critical Tol= 0.01
Num of Std Step Trials= 20
Max Error Tol= 0.3
Flow Tol Ratio= 0.001
Split Flow NTrial= 30
Split Flow Tol= 0.02
Split Flow Ratio= 0.02
Log Output Level= 0
Friction Slope Method= 1
Unsteady Friction Slope Method= 2
Unsteady Bridges Friction Slope Method= 1
Parabolic Critical Depth
Global Vel Dist=  1 , 1 , 1
Global Log Level= 0
CheckData=True
Encroach Param= -1, 0, 0, 0
BEGIN DESCRIPTION:
Multiple Run
END DESCRIPTION:

--- Stream0070.f01 (steady flow) ---

Flow Title=Multiple
Number of Profiles=7
Profile Names=10-year,25-year,50-year,1pct_min,100-year,1pct_plu,500-year
River Rch & RM= Stream0070,Reach-1,16870
    1490    2633    3765    2612    5211   10397    9904
River Rch & RM= Stream0070,Reach-1,14428
    1709    3033    4351    3024    6034   12040   11523
River Rch & RM= Stream0070,Reach-1,11404
    1941    3466    4990    3480    6943   13854   13347
River Rch & RM= Stream0070,Reach-1,10071
    2129    3796    5462    3805    7592   15148   14558
River Rch & RM= Stream0070,Reach-1,7179
    2525    4533    6550    4580    9138   18233   17655
River Rch & RM= Stream0070,Reach-1,4256
    2645    4752    6870    4803    9584   19123   18520
River Rch & RM= Stream0070,Reach-1,1468
    3384    6125    8897    6239   12448   24837   24155
Boundary for River Rch & Prof#=Stream0070,Reach-1,1
Up Type=0
Dn Type=3
Dn Slope=0.005
Boundary for River Rch & Prof#=Stream0070,Reach-1,2
Up Type=0
Dn Type=3
Dn Slope=0.005
Boundary for River Rch & Prof#=Stream0070,Reach-1,3
Up Type=0
Dn Type=3
Dn Slope=0.005
Boundary for River Rch & Prof#=Stream0070,Reach-1,4
Up Type=0
Dn Type=3
Dn Slope=0.005
Boundary for River Rch & Prof#=Stream0070,Reach-1,5
Up Type=0
Dn Type=3
Dn Slope=0.005
Boundary for River Rch & Prof#=Stream0070,Reach-1,6
Up Type=0
Dn Type=3
Dn Slope=0.005
Boundary for River Rch & Prof#=Stream0070,Reach-1,7
Up Type=0
Dn Type=3
Dn Slope=0.005

--- Stream0070.g01 (geometry) ---

Geom Title=Existing Conditions
Program Version=4.10

River Reach=Stream0070      ,Reach-1
Reach XY= 30
        1988025.       13921025.       1987675.5     13920359.79
      1987624.64     13918654.85      1987723.78      13918085.5
      1987374.89      13917445.1      1987580.54     13916872.58
      1987718.52     13916682.69      1987964.68     13916635.18
      1987980.47     13916372.55      1988572.94     13915519.14
      1988524.47     13913985.47      1988328.53     13913823.55
      1988321.26     13913426.52      1988024.77     13912949.93
      1988188.31     13912611.66       1988422.5     13912466.85
      1988528.44     13911876.22      1988717.44       13911625.
      1988619.81     13911280.44      1988031.19     13910782.81
      1987622.57     13910669.48      1987432.81     13910481.19
      1987467.19     13910271.59      1987178.55     13909773.53
      1987174.57     13909504.82        1987825.       13908625.
      1987780.47     13907772.55      1987930.71     13907576.88
      1988135.02     13907664.05        1988375.       13907375.

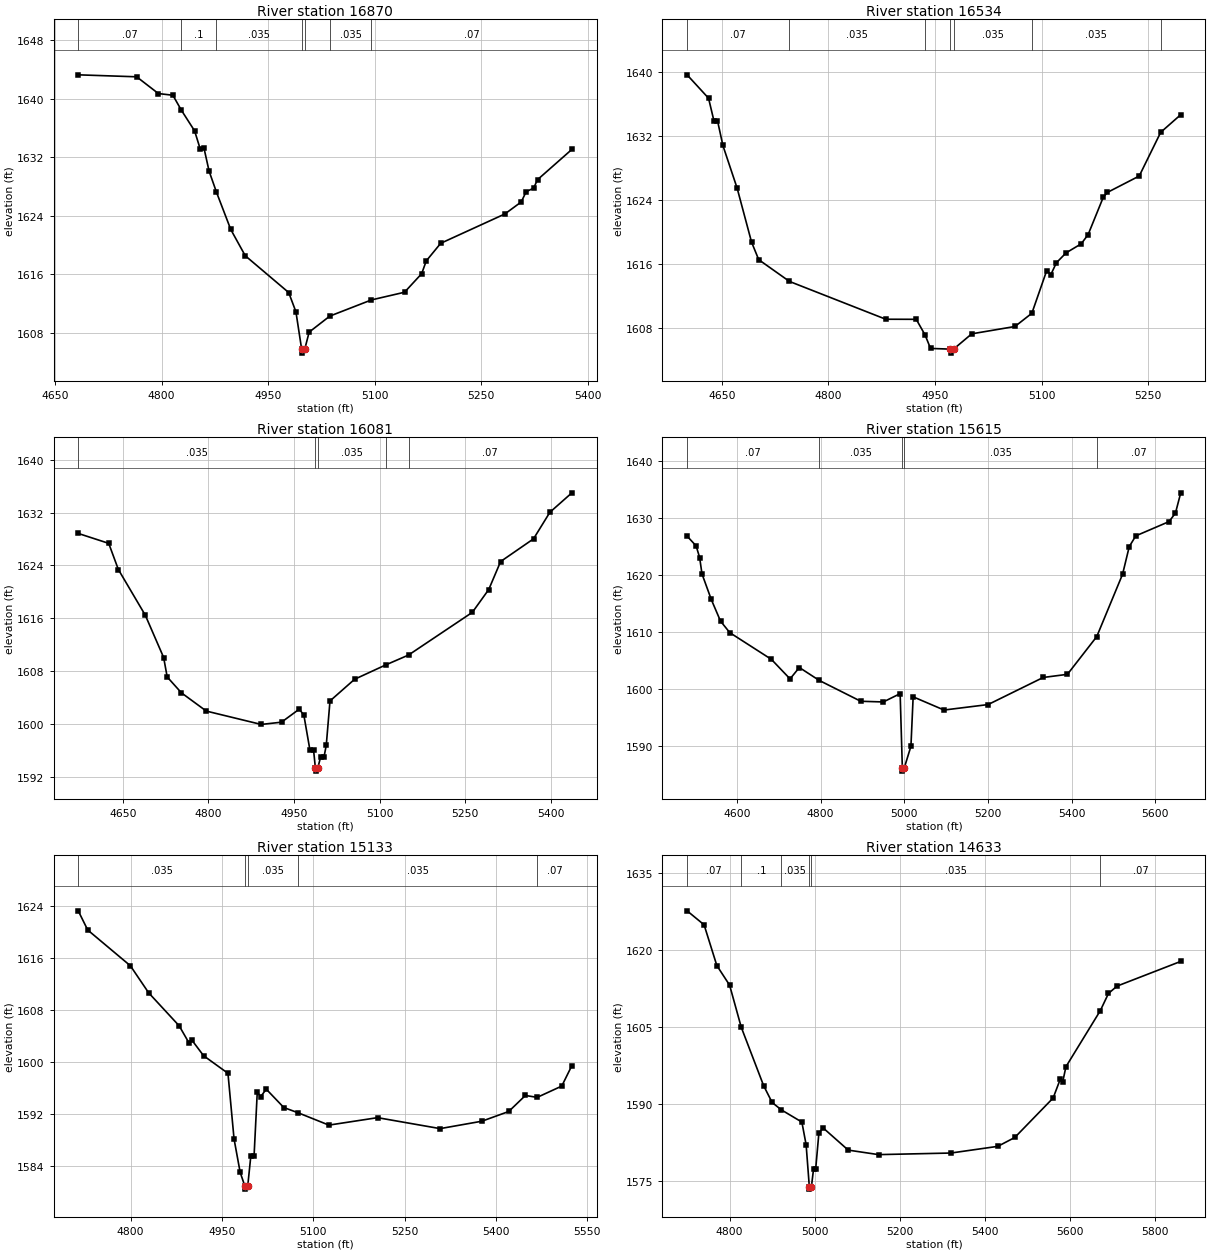
Type RM Length L Ch R = 1 ,16870   ,336,336,336
BEGIN DESCRIPTION:
Stream0070 34.0
END DESCRIPTION:
XS GIS Cut Line= 3
      1988335.71     13920925.88      1987825.26     13921027.45
      1987666.45     13921100.35
#Sta/Elev= 30
  4682.7 1643.24    4765 1642.97  4795.6 1640.68    4816 1640.45  4827.8 1638.43
  4846.6 1635.58  4854.6 1633.07  4859.7 1633.27    4867 1630.08  4877.4  1627.2
  4897.5 1622.11  4917.9 1618.52  4979.1 1613.49  4989.3 1610.85  4997.4 1605.71
  4997.7 1605.21  5001.6 1605.71  5007.9 1608.08    5037 1610.27  5095.6 1612.48
  5142.2 1613.53  5166.4 1616.07  5172.8 1617.81  5193.2 1620.22  5283.6 1624.23
  5306.6 1625.87  5313.5 1627.27    5324 1627.75  5329.5 1628.91  5377.9 1633.05
#Mann= 7 ,-1 , 0
  4682.7     .07       0  4827.8      .1       0  4877.4    .035       0
  4997.4    .035       0  5001.6    .035       0    5037    .035       0
  5095.6     .07       0
Bank Sta=4997.4,5001.6
XS Rating Curve= 0 ,0
Exp/Cntr=0.3,0.1

Type RM Length L Ch R = 1 ,16534   ,453,453,453
BEGIN DESCRIPTION:
Stream0070 33.0
END DESCRIPTION:
XS GIS Cut Line= 3
      1988224.99       13920675.        1987825.       13920725.
      1987574.96     13920875.03
#Sta/Elev= 30
  4601.2  1639.7  4631.4 1636.77    4639 1633.93    4644 1633.95  4651.6 1630.84
  4671.7 1625.47  4691.9 1618.73    4702 1616.52  4745.3 1613.79  4880.8 1609.05
  4923.7 1609.04  4936.1 1607.08  4943.8 1605.39  4971.9  1605.3  4972.2  1604.8
  4976.2  1605.3  5001.8 1607.22  5062.6 1608.14  5086.4  1609.8  5107.3 1615.15
  5113.1 1614.64  5120.9 1616.13  5134.5 1617.37  5155.9 1618.51  5165.6 1619.67
    5187 1624.37  5192.8 1624.96  5237.5 1627.01  5267.7 1632.49  5295.9  1634.7
#Mann= 7 ,-1 , 0
  4601.2     .07       0  4745.3    .035       0  4936.1    .035       0
  4971.9    .035       0  4976.2    .035       0  5086.4    .035       0
  5267.7     .07       0
Bank Sta=4971.9,4976.2
XS Rating Curve= 0 ,0
Exp/Cntr=0.3,0.1

Type RM Length L Ch R = 1 ,16081   ,466,466,466
BEGIN DESCRIPTION:
Stream0070 32.0
END DESCRIPTION:
XS GIS Cut Line= 3
      1988075.04     13920174.99        1987675.       13920325.
      1987399.57     13920664.61
#Sta/Elev= 30
  4572.1 1628.84  4625.5 1627.34  4642.4 1623.38  4689.6 1616.47  4721.7 1610.08
  4727.9 1607.14  4752.8 1604.74  4796.4 1601.98  4892.5 1599.96  4928.1  1600.3
  4959.3 1602.28  4967.3 1601.34    4978 1596.02  4984.2 1596.12  4987.4  1593.4
  4987.7  1592.9  4991.7  1593.4  4996.7 1595.07  5002.6 1595.07  5006.5 1596.84
    5013 1603.51  5056.1 1606.79  5110.4 1608.95  5150.5 1610.45  5262.3 1616.91
    5291 1620.36  5311.8 1624.59  5369.4 1628.02  5398.1 1632.04  5436.6 1634.98
#Mann= 5 ,-1 , 0
  4572.1    .035       0  4987.4    .035       0  4991.7    .035       0
  5110.4    .035       0  5150.5     .07       0
Bank Sta=4987.4,4991.7
XS Rating Curve= 0 ,0
Exp/Cntr=0.3,0.1

Type RM Length L Ch R = 1 ,15615   ,482,482,482
BEGIN DESCRIPTION:
Stream0070 31.0
END DESCRIPTION:
XS GIS Cut Line= 4
       1988194.2     13920074.95      1987794.18     13919869.32
        1987725.       13919875.      1987098.35      13920084.1
#Sta/Elev= 30
  4480.9 1626.83  4502.5 1625.11  4510.9 1623.07  4516.5  1620.2  4538.7  1615.7
  4560.8  1611.9    4583 1609.87  4682.4 1605.18    4727 1601.75  4749.2 1603.75
  4796.8 1601.48    4896 1597.82  4949.9  1597.7  4990.1 1599.16  4995.4 1586.05
  4995.7 1585.55  4999.7 1586.05  5015.9 1589.92  5021.2  1598.6    5095 1596.28
  5200.3 1597.24    5332    1602  5389.9 1602.55    5460 1609.18  5521.7 1620.13
  5537.7 1624.99  5553.3 1626.87  5632.6 1629.37  5648.1 1630.87  5660.7 1634.43
#Mann= 5 ,-1 , 0
  4480.9     .07       0  4796.8    .035       0  4995.4    .035       0
  4999.7    .035       0    5460     .07       0
Bank Sta=4995.4,4999.7
XS Rating Curve= 0 ,0
Exp/Cntr=0.3,0.1

Type RM Length L Ch R = 1 ,15133   ,500,500,500
BEGIN DESCRIPTION:
Stream0070 30.0
END DESCRIPTION:
XS GIS Cut Line= 3
      1987910.53     13919438.86        1987625.       13919425.
      1987165.57      13919678.1
#Sta/Elev= 30
  4714.1 1623.28  4729.7 1620.32  4799.7 1614.81  4829.8 1610.63  4879.8 1605.55
  4895.8 1602.94  4900.9 1603.32  4919.9 1600.94  4959.9 1598.23  4969.9 1588.11
  4979.9 1582.98  4987.5 1580.87  4987.9 1580.37  4992.4 1580.87  4997.5 1585.53
  5002.8 1585.53    5008 1595.29  5013.7 1594.64  5022.8 1595.78  5051.6 1592.95
  5075.4 1592.13  5125.6 1590.24  5205.5 1591.39  5308.2  1589.7  5376.7 1590.84
  5420.8 1592.34  5448.2 1594.81  5467.6 1594.52  5507.9 1596.26  5524.5 1599.42
#Mann= 5 ,-1 , 0
  4714.1    .035       0  4987.5    .035       0  4992.4    .035       0
  5075.4    .035       0  5467.6     .07       0
Bank Sta=4987.5,4992.4
XS Rating Curve= 0 ,0
Exp/Cntr=0.3,0.1

Type RM Length L Ch R = 1 ,14633   ,205,205,205
BEGIN DESCRIPTION:
Stream0070 29.0
END DESCRIPTION:
XS GIS Cut Line= 3
      1987924.99       13918925.        1987625.       13918925.
      1986765.46     13918976.91
#Sta/Elev= 30
    4700 1627.63    4740 1624.91    4770 1616.97    4800 1613.16  4827.4 1604.96
    4880 1593.59    4900 1590.31  4921.7 1588.87    4970 1586.49    4980 1582.08
  4987.5 1573.93  4987.9 1573.43  4992.5 1573.93  4997.5 1577.37  5002.5 1577.37
    5010 1584.34    5020 1585.35    5079 1581.03  5150.3 1580.15  5320.6 1580.46
  5430.8 1581.76  5470.8 1583.49    5561 1591.18  5578.3 1594.96  5583.3 1594.23
  5591.1 1597.27    5672  1608.2  5691.2 1611.55  5711.3 1612.97  5861.1 1617.78
#Mann= 6 ,-1 , 0
    4700     .07       0  4827.4      .1       0  4921.7    .035       0
  4987.5    .035       0  4992.5    .035       0    5672     .07       0
Bank Sta=4987.5,4992.5
XS Rating Curve= 0 ,0
Exp/Cntr=0.3,0.1

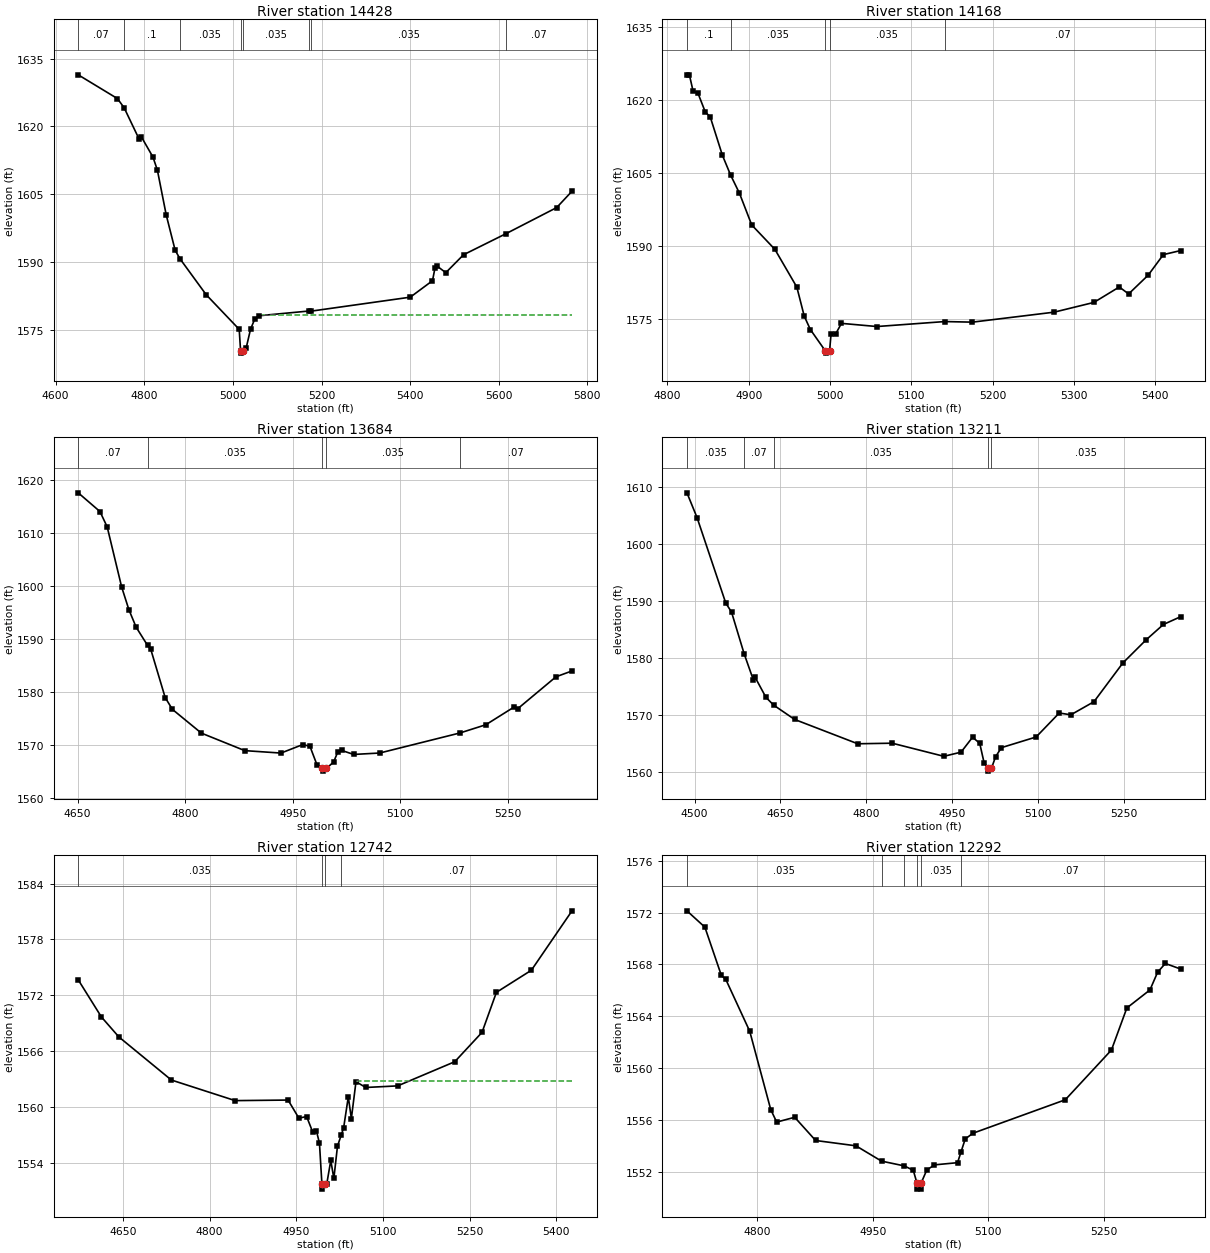
Type RM Length L Ch R = 1 ,14428   ,260,260,260
BEGIN DESCRIPTION:
Mapping XS adedadd6
END DESCRIPTION:
XS GIS Cut Line= 2
      1987973.44     13918736.38      1986860.48     13918686.06
#Sta/Elev= 30
  4651.1 1631.41  4739.6 1626.15  4754.8  1624.1  4788.5 1617.18  4793.5 1617.69
  4819.7 1613.22  4829.7 1610.32  4849.7 1600.38  4869.8 1592.59    4881 1590.67
  4939.8 1582.76  5014.3  1575.1  5017.4 1570.34  5017.8 1569.84  5022.4 1570.34
  5029.9 1570.92  5039.9 1575.14  5049.9 1577.48    5060 1578.12    5171 1579.15
    5176 1579.12  5400.3 1582.22  5450.4 1585.86    5456 1588.65    5461 1589.08
  5480.4 1587.64  5520.4  1591.6  5616.9  1596.3  5730.6 1602.04  5765.2 1605.66
#Mann= 8 ,-1 , 0
  4651.1     .07       0  4754.8      .1       0    4881    .035       0
  5017.4    .035       0  5022.4    .035       0    5171     .07       0
    5176    .035       0  5616.9     .07       0
#XS Ineff= 2 , 0
                         5066.28          1578.2
Permanent Ineff=
       F       F
Bank Sta=5017.4,5022.4
XS Rating Curve= 0 ,0
Exp/Cntr=0.3,0.1

Type RM Length L Ch R = 1 ,14168   ,484,484,484
BEGIN DESCRIPTION:
Stream0070 28.0
END DESCRIPTION:
XS GIS Cut Line= 3
      1987825.03     13918575.02        1987675.       13918475.
      1987275.01       13918325.
#Sta/Elev= 30
    4824 1625.09    4827 1625.09  4831.5 1621.78  4837.6  1621.3  4846.6 1617.44
  4852.6 1616.48  4867.6 1608.58  4877.7 1604.52  4888.6 1600.78  4903.7 1594.27
  4932.2 1589.26  4959.2 1581.51  4968.3 1575.56  4975.8 1572.81  4994.1 1568.46
  4994.5 1567.96  4999.5 1568.46  5001.3 1571.91    5007 1571.91  5014.1 1574.07
  5057.7 1573.42  5141.2 1574.44  5175.2 1574.32  5275.8 1576.37  5324.7 1578.37
  5355.9 1581.54  5367.4 1580.11  5391.5 1583.97  5410.1 1588.18  5431.5 1589.02
#Mann= 5 ,-1 , 0
    4824      .1       0  4877.7    .035       0  4994.1    .035       0
  4999.5    .035       0  5141.2     .07       0
Bank Sta=4994.1,4999.5
XS Rating Curve= 0 ,0
Exp/Cntr=0.3,0.1

Type RM Length L Ch R = 1 ,13684   ,473,473,473
BEGIN DESCRIPTION:
Stream0070 27.0
END DESCRIPTION:
XS GIS Cut Line= 3
      1988025.04     13917974.99        1987675.       13918025.
        1987375.       13918175.
#Sta/Elev= 30
  4650.8  1617.6  4681.1 1614.07  4691.2 1611.17  4711.4 1599.81  4721.5 1595.53
  4731.6 1592.23  4747.5  1588.8  4751.9  1588.1  4772.1 1578.95  4782.2 1576.71
  4822.6 1572.23  4883.2 1568.92  4933.7 1568.46    4964 1570.06  4974.1 1569.75
  4984.2 1566.14  4991.5 1565.55  4991.9 1565.05  4997.1 1565.55  5007.2 1566.79
  5012.8 1568.61  5018.4 1568.96  5035.1  1568.2  5071.5 1568.47  5183.8 1572.27
  5219.6 1573.81  5258.7 1577.13  5264.3 1576.86  5317.4 1582.86  5339.8 1583.97
#Mann= 5 ,-1 , 0
  4650.8     .07       0  4747.5    .035       0  4991.5    .035       0
  4997.1    .035       0  5183.8     .07       0
Bank Sta=4991.5,4997.1
XS Rating Curve= 0 ,0
Exp/Cntr=0.3,0.1

Type RM Length L Ch R = 1 ,13211   ,469,469,469
BEGIN DESCRIPTION:
Stream0070 26.0
END DESCRIPTION:
XS GIS Cut Line= 3
      1987982.63     13917592.36        1987475.       13917625.
      1987125.03       13917675.
#Sta/Elev= 30
  4486.8  1608.9  4504.5 1604.54  4554.6 1589.55  4564.6 1587.99  4586.7 1580.65
  4602.8 1576.06  4605.9 1576.52  4624.7 1573.02  4638.2 1571.65  4674.8 1569.14
    4785 1564.87  4845.2 1564.97  4935.4 1562.67  4965.4  1563.4  4985.5 1566.01
    4998 1564.96  5005.6 1561.56  5012.9 1560.57  5013.3 1560.07  5018.5 1560.57
  5025.8 1562.61  5035.9 1564.19  5096.5 1566.06  5136.9 1570.27  5157.1 1569.95
  5197.5 1572.25    5248 1579.05  5288.4 1583.09  5318.7  1585.8    5349 1587.17
#Mann= 5 ,-1 , 0
  4486.8    .035       0  4586.7     .07       0  4638.2    .035       0
  5012.9    .035       0  5018.5    .035       0
Bank Sta=5012.9,5018.5
XS Rating Curve= 0 ,0
Exp/Cntr=0.3,0.1

Type RM Length L Ch R = 1 ,12742   ,450,450,450
BEGIN DESCRIPTION:
Stream0070 25.0
END DESCRIPTION:
XS GIS Cut Line= 3
        1987875.       13917375.        1987475.       13917225.
        1987075.       13917375.
#Sta/Elev= 30
  4572.8 1573.67  4612.9 1569.69  4643.1 1567.55  4733.9 1562.93  4844.3 1560.72
  4935.9 1560.78  4954.6 1558.84    4968 1559.01  4978.6 1557.34  4984.9 1557.48
  4990.2 1556.16  4994.5 1551.73  4994.9 1551.23  5000.2 1551.73  5002.7 1551.73
  5009.8 1554.31  5015.1 1552.37  5021.4 1555.84    5028 1557.05    5032 1557.79
  5040.1 1561.12  5045.4  1558.8  5053.4 1562.75  5070.3 1562.13  5125.5  1562.3
  5224.3 1564.89  5271.5 1568.04  5296.4 1572.33  5356.9  1574.7  5427.2 1581.07
#Mann= 4 ,-1 , 0
  4572.8    .035       0  4994.5    .035       0  5000.2    .035       0
    5028     .07       0
#XS Ineff= 2 , 0
         4935.86 1560.76 5054.55         1562.85
Permanent Ineff=
       F       F
Bank Sta=4994.5,5000.2
XS Rating Curve= 0 ,0
Exp/Cntr=0.3,0.1

Type RM Length L Ch R = 1 ,12292   ,453,453,453
BEGIN DESCRIPTION:
Stream0070 24.0
END DESCRIPTION:
XS GIS Cut Line= 3
      1987875.01     13916975.01        1987625.       13916825.
      1987274.96       13916825.
#Sta/Elev= 30
  4708.4 1572.13  4731.7 1570.87  4753.1 1567.15  4758.9 1566.84    4790 1562.84
  4817.3  1556.8    4825 1555.84  4848.4 1556.21  4875.6 1554.42    4928 1554.01
  4961.2 1552.83  4990.9 1552.46  5002.5 1552.12  5007.1 1551.17  5007.6 1550.67
  5012.4 1550.67  5012.9 1551.17    5020 1552.14    5030 1552.54    5060 1552.71
  5064.7 1553.57    5070 1554.54    5080 1554.98    5200 1557.56    5260  1561.4
    5280 1564.64    5310 1566.03    5320  1567.4    5330 1568.07    5350 1567.64
#Mann= 6 ,-1 , 0
  4708.4    .035       0  4961.2     .07       0  4990.9    .035       0
  5007.1    .035       0  5012.9    .035       0  5064.7     .07       0
Bank Sta=5007.1,5012.9
XS Rating Curve= 0 ,0
Exp/Cntr=0.3,0.1

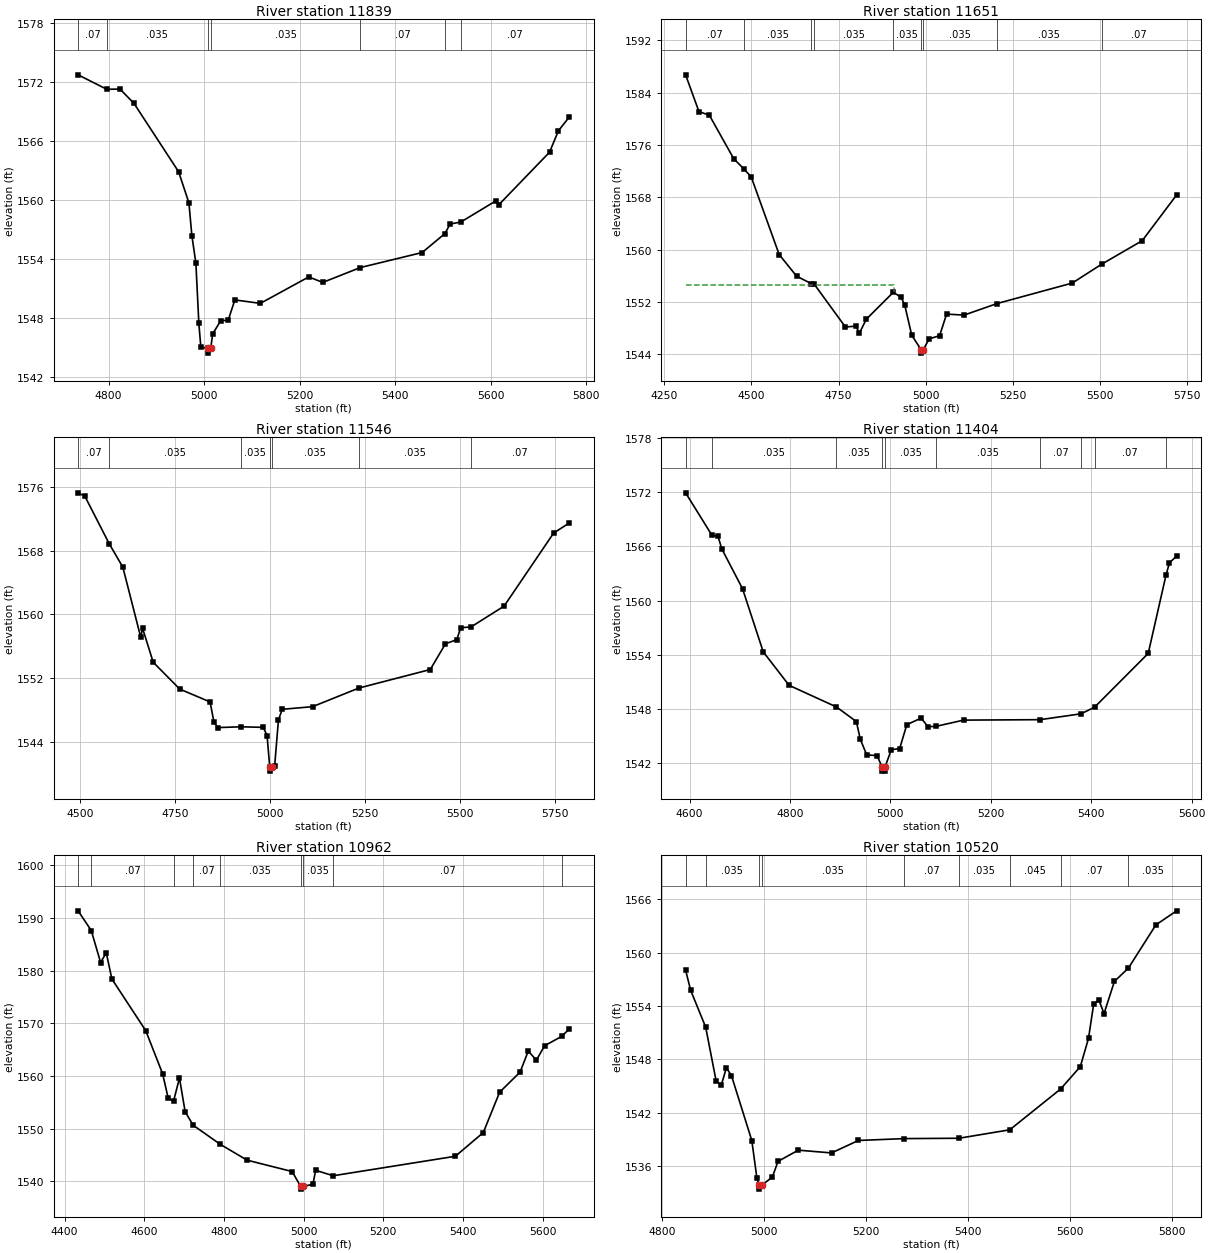
Type RM Length L Ch R = 1 ,11839   ,188,188,188
BEGIN DESCRIPTION:
Stream0070 23.0
END DESCRIPTION:
XS GIS Cut Line= 3
      1988129.21     13916834.51        1987975.       13916625.
      1987264.67     13916333.39
#Sta/Elev= 30
  4736.2 1572.68  4796.3 1571.21    4824 1571.23  4853.3 1569.77  4946.7 1562.82
  4968.2 1559.66  4974.4 1556.33  4982.8 1553.53    4989 1547.42  4993.2 1544.98
  5008.1 1544.88  5008.6 1544.38  5013.9 1544.88    5018 1546.34    5035 1547.69
  5050.4 1547.72  5064.4 1549.79  5117.8 1549.44  5219.1 1552.13  5248.4 1551.57
    5327 1553.08  5456.5 1554.61    5504 1556.53  5515.2 1557.51  5537.4 1557.71
  5611.1 1559.87  5616.5 1559.44  5723.2 1564.81  5741.8 1566.99  5764.2 1568.37
#Mann= 7 ,-1 , 0
  4736.2     .07       0  4796.3    .035       0  5008.1    .035       0
  5013.9    .035       0    5327     .07       0    5504    .035       0
  5537.4     .07       0
Bank Sta=5008.1,5013.9
XS Rating Curve= 0 ,0
Exp/Cntr=0.3,0.1

Type RM Length L Ch R = 1 ,11651   ,105,105,105
BEGIN DESCRIPTION:
Stream0070 22.2
END DESCRIPTION:
XS GIS Cut Line= 4
      1988663.21     13916449.91      1987707.98     13916429.81
      1987522.51     13916418.54      1987278.55     13916310.65
#Sta/Elev= 30
  4311.3 1586.73  4349.5 1581.12  4379.5 1580.55  4449.5 1573.89  4478.8 1572.33
  4499.5 1571.12  4579.6 1559.26  4629.6 1555.95  4671.5 1554.82    4680 1554.74
  4769.6 1548.18  4799.6 1548.32  4809.6 1547.24  4829.6 1549.38  4907.1  1553.5
  4929.6  1552.7  4939.6 1551.54  4959.7 1546.93  4986.8 1544.69  4987.2 1544.19
  4992.6 1544.69  5009.7 1546.37  5039.7 1546.86  5059.7 1550.16  5109.7    1550
  5204.5 1551.77    5420  1554.9    5504 1557.77  5620.7 1561.38  5719.3 1568.37
#Mann= 9 ,-1 , 0
  4311.3     .07       0  4478.8    .035       0  4671.5     .07       0
    4680    .035       0  4907.1    .035       0  4986.8    .035       0
  4992.6    .035       0  5204.5    .035       0    5504     .07       0
#XS Ineff= 2 , 0
         4908.09 1554.67
Permanent Ineff=
       F       F
Bank Sta=4986.8,4992.6
XS Rating Curve= 0 ,0
Exp/Cntr=0.3,0.1

Type RM Length L Ch R = 1 ,11546   ,142,142,142
BEGIN DESCRIPTION:
Stream0070 22.1
END DESCRIPTION:
XS GIS Cut Line= 3
      1988512.82     13916353.84      1987469.18     13916329.86
      1987233.75     13916245.52
#Sta/Elev= 30
  4494.3 1575.22  4512.1  1574.8  4576.5 1568.83  4612.2 1565.92  4659.3 1557.15
  4664.3 1558.26  4692.2 1554.01  4762.2 1550.65  4842.2 1549.04  4852.2 1546.53
  4862.2 1545.83  4923.1 1545.93  4982.3 1545.86  4992.3 1544.84  4999.4 1540.88
  4999.8 1540.38  5005.2 1540.88  5012.3 1541.04  5022.3 1546.79  5032.3 1548.12
  5112.3 1548.45  5234.2 1550.78  5422.4  1553.1  5462.4 1556.32  5492.4 1556.84
  5502.4 1558.33  5529.8 1558.43    5617 1561.04  5747.6 1570.19  5788.3 1571.43
#Mann= 7 ,-1 , 0
  4494.3     .07       0  4576.5    .035       0  4923.1    .035       0
  4999.4    .035       0  5005.2    .035       0  5234.2    .035       0
  5529.8     .07       0
Bank Sta=4999.4,5005.2
XS Rating Curve= 0 ,0
Exp/Cntr=0.3,0.1

Type RM Length L Ch R = 1 ,11404   ,442,442,442
BEGIN DESCRIPTION:
Stream0070 22.0
END DESCRIPTION:
XS GIS Cut Line= 3
      1988474.97     13916324.99        1988075.       13916225.
      1987674.98     13915824.98
#Sta/Elev= 30
  4592.1 1571.95  4644.8 1567.22  4656.5 1567.15  4664.2 1565.73  4705.5 1561.31
  4746.7 1554.31  4798.2 1550.59  4892.6 1548.19  4932.2 1546.57    4940 1544.62
  4952.8 1542.87  4973.5 1542.79  4983.1 1541.57  4983.6 1541.07  4989.1 1541.07
  4989.6 1541.57  5001.8 1543.45  5018.5 1543.58  5032.7 1546.22    5061 1546.95
  5075.1    1546  5090.9 1546.04  5145.8 1546.73  5298.2 1546.78  5379.6 1547.43
  5406.6 1548.16  5513.5 1554.13    5549 1562.83  5555.9  1564.2  5570.1 1564.92
#Mann= 10 ,-1 , 0
  4592.1     .07       0  4644.8    .035       0  4892.6    .035       0
  4983.1    .035       0  4989.6    .035       0  5090.9    .035       0
  5298.2     .07       0  5379.6    .035       0  5406.6     .07       0
    5549    .035       0
Bank Sta=4983.1,4989.6
XS Rating Curve= 0 ,0
Exp/Cntr=0.3,0.1

Type RM Length L Ch R = 1 ,10962   ,442,442,442
BEGIN DESCRIPTION:
Stream0070 21.0
END DESCRIPTION:
XS GIS Cut Line= 3
      1988724.96     13916274.96        1988325.       13915875.
      1987675.02       13915725.
#Sta/Elev= 30
  4434.1 1591.38  4467.2 1587.64  4490.6 1581.56  4504.8 1583.43  4518.9 1578.44
  4603.8 1568.64  4646.2 1560.46  4660.3  1555.8  4673.7 1555.22  4688.6 1559.64
  4702.8 1553.24    4723 1550.66  4790.8 1547.05  4858.3 1544.03  4971.5 1541.87
  4992.9 1539.03  4993.4 1538.53  4999.5 1539.03  5023.7 1539.47  5030.5 1542.11
  5074.4 1541.07  5381.2 1544.77  5451.3 1549.27  5492.4 1556.94  5543.7 1560.75
  5564.2 1564.75  5584.7 1563.01  5605.2 1565.76  5647.9 1567.52  5666.8 1568.92
#Mann= 9 ,-1 , 0
  4434.1    .035       0  4467.2     .07       0  4673.7    .035       0
    4723     .07       0  4790.8    .035       0  4992.9    .035       0
  4999.5    .035       0  5074.4     .07       0  5647.9    .035       0
Bank Sta=4992.9,4999.5
XS Rating Curve= 0 ,0
Exp/Cntr=0.3,0.1

Type RM Length L Ch R = 1 ,10520   ,449,449,449
BEGIN DESCRIPTION:
Stream0070 20.0
END DESCRIPTION:
XS GIS Cut Line= 3
      1988725.02       13915525.        1988575.       13915525.
      1987774.96     13915374.99
#Sta/Elev= 30
    4846 1558.02    4856 1555.74  4885.4 1551.62    4906 1545.54    4916 1545.08
    4926 1547.04    4936 1546.17    4976 1538.86    4986 1534.63  4990.1  1533.9
  4990.6  1533.4  4996.9  1533.9  5016.4 1534.76  5027.4 1536.52  5067.2 1537.78
  5132.5 1537.47  5185.1 1538.87    5275 1539.08  5382.7 1539.12  5482.4 1540.07
  5582.1 1544.65  5620.9 1547.17    5637 1550.35  5647.2 1554.23  5657.4 1554.66
  5667.5 1553.14  5687.9 1556.76  5715.3 1558.25  5769.3 1563.11    5810 1564.69
#Mann= 9 ,-1 , 0
    4846     .07       0  4885.4    .035       0  4990.1    .035       0
  4996.9    .035       0    5275     .07       0  5382.7    .035       0
  5482.4    .045       0  5582.1     .07       0  5715.3    .035       0
Bank Sta=4990.1,4996.9
XS Rating Curve= 0 ,0
Exp/Cntr=0.3,0.1

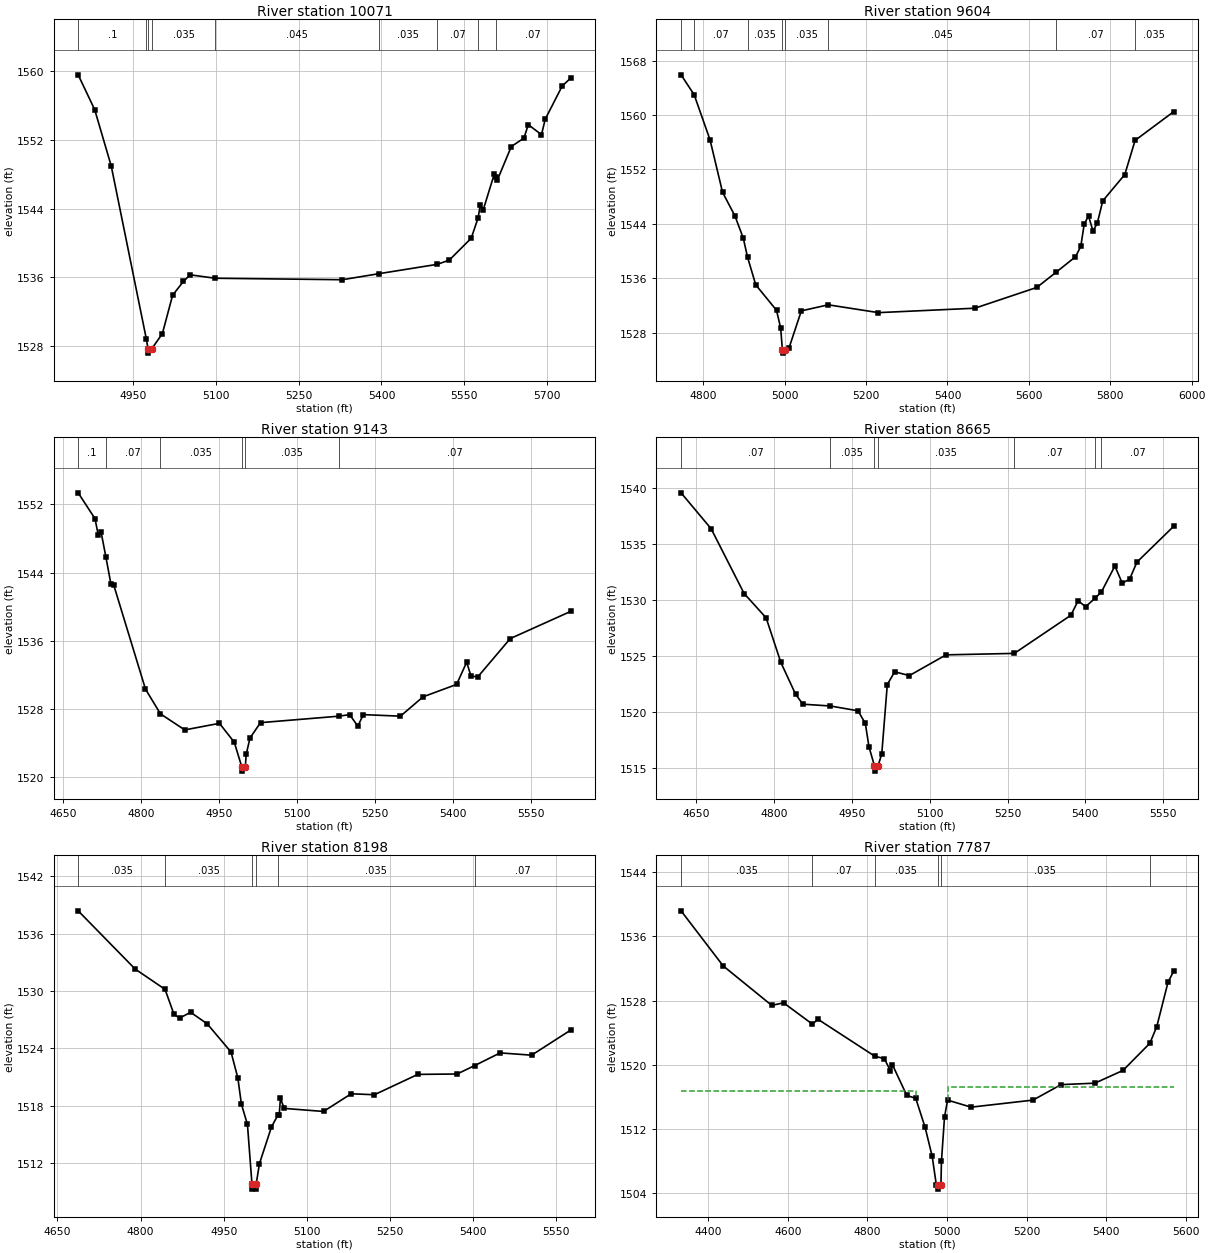
Type RM Length L Ch R = 1 ,10071   ,467,467,467
BEGIN DESCRIPTION:
Stream0070 19.0
END DESCRIPTION:
XS GIS Cut Line= 3
      1988725.01       13915075.        1988575.       13915075.
      1987875.02     13915324.99
#Sta/Elev= 30
    4850 1559.59    4880 1555.53    4910 1548.96  4973.8 1528.77  4976.6 1527.68
  4977.1 1527.18  4983.4 1527.68  5002.7 1529.45  5021.3 1533.93  5040.9 1535.53
  5053.1  1536.3  5098.5  1535.9  5329.2 1535.73  5395.3 1536.43  5501.2 1537.52
    5523 1538.01  5562.8 1540.56  5575.3 1542.93  5579.3 1544.44  5584.6 1543.87
  5604.7 1548.05  5607.1 1547.73  5610.1 1547.32  5635.5 1551.24  5658.4 1552.22
  5666.3 1553.79  5690.2 1552.62  5697.1 1554.43  5727.9  1558.3  5743.3 1559.21
#Mann= 9 ,-1 , 0
    4850      .1       0  4973.8    .035       0  4976.6    .035       0
  4983.4    .035       0  5098.5    .045       0  5395.3    .035       0
  5501.2     .07       0  5575.3    .035       0  5607.1     .07       0
Bank Sta=4976.6,4983.4
XS Rating Curve= 0 ,0
Exp/Cntr=0.3,0.1

Type RM Length L Ch R = 1 ,9604    ,461,461,461
BEGIN DESCRIPTION:
Stream0070 18.0
END DESCRIPTION:
XS GIS Cut Line= 4
      1988774.96     13914674.99        1988525.       13914625.
      1988419.08     13914642.56      1987630.92     13914955.27
#Sta/Elev= 30
  4745.5 1565.93  4777.7    1563  4816.8 1556.34  4847.4 1548.65    4878 1545.15
  4898.4 1541.89  4908.8 1539.11    4929 1535.02    4980 1531.28  4990.2 1528.67
  4994.5 1525.47    4995 1524.97  5001.3 1525.47  5010.5 1525.69    5041 1531.19
  5107.2 1532.08  5230.5 1530.93  5467.2 1531.58  5619.6 1534.64  5666.7 1536.86
  5714.6 1539.15  5727.6 1540.68  5736.1 1543.99  5746.6 1545.15  5757.7 1542.93
  5768.4 1544.15  5781.6 1547.38  5835.7 1551.25    5861 1556.28  5955.7  1560.5
#Mann= 8 ,-1 , 0
  4745.5      .1       0  4777.7     .07       0  4908.8    .035       0
  4994.5    .035       0  5001.3    .035       0  5107.2    .045       0
  5666.7     .07       0    5861    .035       0
Bank Sta=4994.5,5001.3
XS Rating Curve= 0 ,0
Exp/Cntr=0.3,0.1

Type RM Length L Ch R = 1 ,9143    ,478,478,478
BEGIN DESCRIPTION:
Stream0070 17.0
END DESCRIPTION:
XS GIS Cut Line= 4
      1988775.02     13914275.01      1988523.15     13914172.75
      1988410.37     13914189.56      1987873.82     13914356.22
#Sta/Elev= 30
  4679.4 1553.34  4711.8 1550.31  4718.2 1548.34  4723.6 1548.71  4732.7 1545.83
  4742.3 1542.69  4747.7 1542.56  4808.9 1530.34  4837.7 1527.44  4884.5 1525.56
  4951.2 1526.33  4979.7 1524.12  4994.2 1521.23  4994.7 1520.73    5001 1521.23
  5002.7  1522.7    5010 1524.61  5030.2 1526.41  5181.3 1527.17  5201.7 1527.35
  5217.5    1526    5228 1527.35  5299.4 1527.17  5343.1 1529.44  5407.5 1530.89
  5426.9  1533.5  5434.9 1531.91  5447.8 1531.74  5510.7 1536.26  5627.1 1539.45
#Mann= 6 ,-1 , 0
  4679.4      .1       0  4732.7     .07       0  4837.7    .035       0
  4994.2    .035       0    5001    .035       0  5181.3     .07       0
Bank Sta=4994.2,5001
XS Rating Curve= 0 ,0
Exp/Cntr=0.3,0.1

Type RM Length L Ch R = 1 ,8665    ,467,467,467
BEGIN DESCRIPTION:
Stream0070 16.0
END DESCRIPTION:
XS GIS Cut Line= 3
      1988591.41     13913549.57        1988325.       13913825.
      1987924.98     13914225.02
#Sta/Elev= 30
  4621.1 1539.54    4679 1536.34  4742.6 1530.56    4785 1528.39  4813.3 1524.42
  4841.6 1521.59  4855.7 1520.69  4908.6 1520.53    4962  1520.1  4976.1 1518.97
  4983.1 1516.89  4993.5 1515.22    4994 1514.72  5000.9 1515.22  5007.8 1516.28
  5018.4 1522.44  5032.6 1523.58  5060.9 1523.24  5131.6 1525.09  5263.1 1525.22
    5372 1528.62  5386.1 1529.92  5400.3 1529.38  5418.6 1530.14    5431 1530.71
  5456.8 1533.01    5471 1531.49  5485.1 1531.83  5499.3 1533.36    5570 1536.55
#Mann= 7 ,-1 , 0
  4621.1     .07       0  4908.6    .035       0  4993.5    .035       0
  5000.9    .035       0  5263.1     .07       0  5418.6    .035       0
    5431     .07       0
Bank Sta=4993.5,5000.9
XS Rating Curve= 0 ,0
Exp/Cntr=0.3,0.1

Type RM Length L Ch R = 1 ,8198    ,411,411,411
BEGIN DESCRIPTION:
Stream0070 15.0
END DESCRIPTION:
XS GIS Cut Line= 4
      1988587.64     13913364.66       1988314.6     13913354.71
      1988232.08     13913388.99      1987875.01     13913774.99
#Sta/Elev= 30
  4687.5 1538.39  4790.2  1532.3  4844.2 1530.17  4860.3 1527.56  4870.3 1527.16
  4890.3 1527.77  4920.3 1526.56  4963.2 1523.61  4975.5 1520.89  4981.9 1518.16
  4992.8 1516.03    5001 1509.76  5001.5 1509.26    5008 1509.26  5008.5 1509.76
  5014.4 1511.92  5036.1 1515.76  5047.9 1517.03  5050.1 1517.03  5052.3 1518.76
  5059.1 1517.71    5130 1517.39  5179.9 1519.24  5221.8 1519.14  5300.1 1521.27
  5370.9 1521.31  5402.9  1522.2  5448.6 1523.52  5505.3 1523.28  5575.9 1525.91
#Mann= 6 ,-1 , 0
  4687.5    .035       0  4844.2    .035       0    5001    .035       0
  5008.5    .035       0  5047.9    .035       0  5402.9     .07       0
Bank Sta=5001,5008.5
XS Rating Curve= 0 ,0
Exp/Cntr=0.3,0.1

Type RM Length L Ch R = 1 ,7787    ,264,264,264
BEGIN DESCRIPTION:
Stream0070 14.0
END DESCRIPTION:
XS GIS Cut Line= 4
      1988600.79     13913327.86      1988181.73     13913035.49
        1988025.       13913075.      1987624.99     13913475.01
#Sta/Elev= 30
  4331.3 1539.19  4437.2 1532.32  4559.3  1527.4    4589 1527.72  4661.5 1525.06
  4675.4 1525.67  4818.4 1521.06  4842.3 1520.76  4857.5 1519.26  4862.7    1520
  4898.6 1516.19  4921.4  1515.8  4944.9 1512.18  4962.6 1508.58    4973 1505.04
    4977 1504.99  4977.5 1504.49  4984.6 1504.99  4985.9 1507.96  4993.6 1513.47
  5001.3 1515.59  5060.5 1514.71    5216 1515.59  5286.7 1517.52  5371.6  1517.7
  5442.3 1519.29  5509.9 1522.68  5527.2 1524.75  5555.4 1530.27  5569.6 1531.67
#Mann= 6 ,-1 , 0
  4331.3    .035       0  4661.5     .07       0  4818.4    .035       0
    4977    .035       0  4984.6    .035       0  5509.9     .07       0
#XS Ineff= 2 , 0
         4921.68 1516.69  5002.8         1517.17
Permanent Ineff=
       F       F
Bank Sta=4977,4984.6
XS Rating Curve= 0 ,0
Exp/Cntr=0.3,0.1

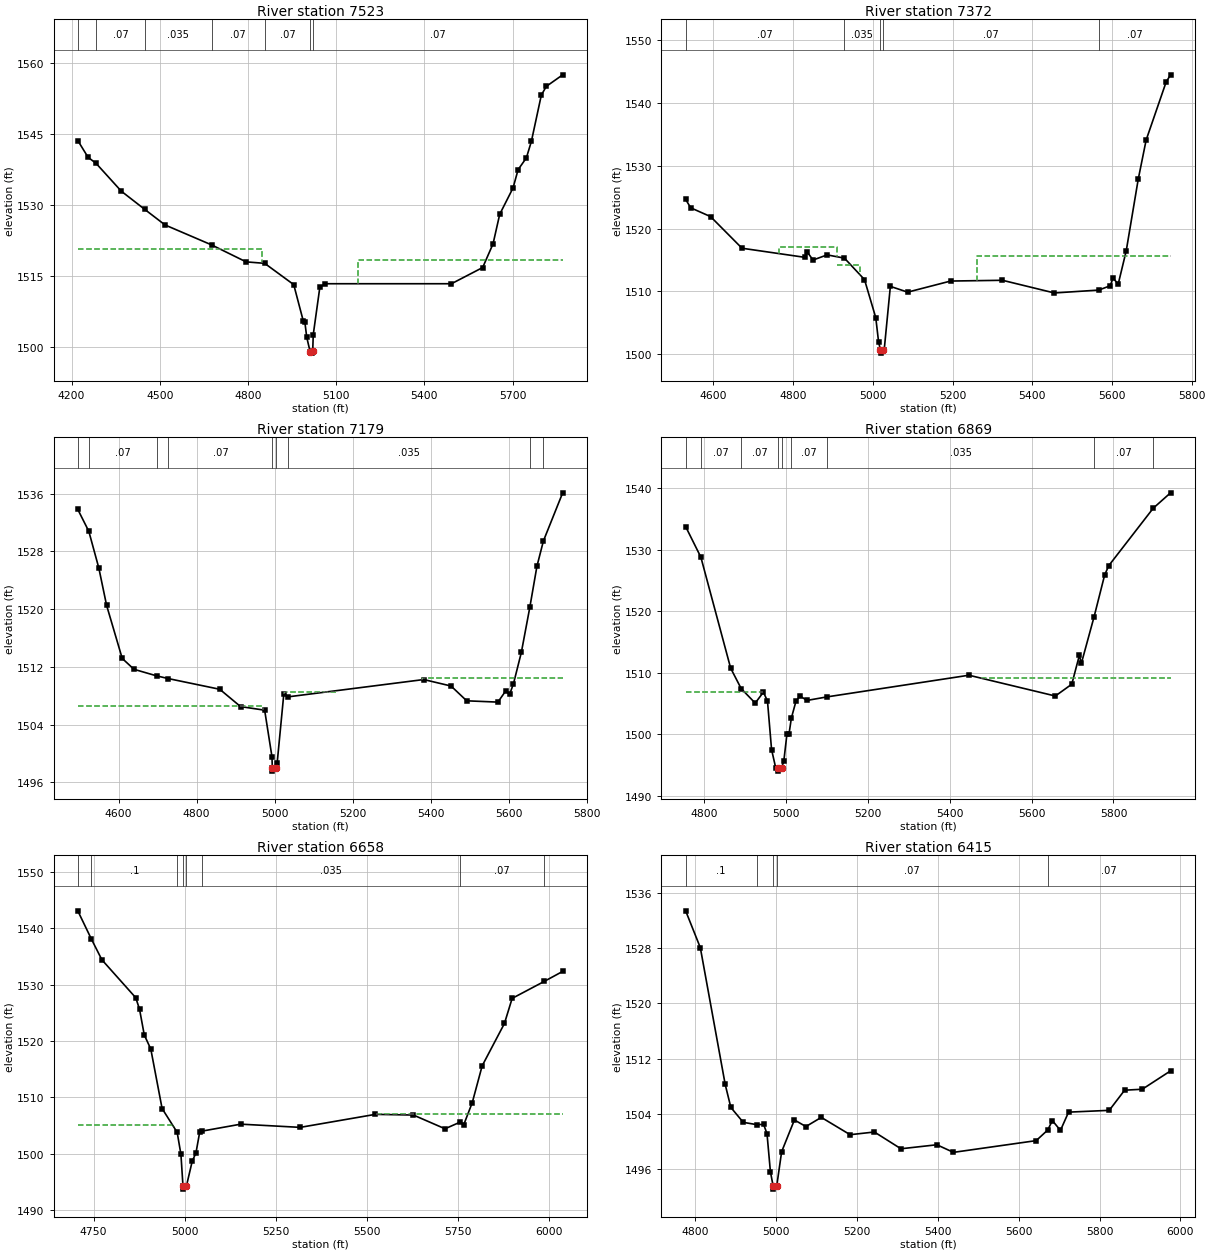
Type RM Length L Ch R = 1 ,7523    ,151,151,151
BEGIN DESCRIPTION:
Stream0070 13.0
END DESCRIPTION:
XS GIS Cut Line= 4
      1988650.58     13913338.92      1988223.56     13912896.98
      1987992.18     13912787.53      1987289.45     13913123.71
#Sta/Elev= 30
  4221.1 1543.63    4256 1540.09  4283.6 1538.78  4369.2  1532.9  4448.6 1529.06
  4517.9 1525.75  4676.8 1521.51  4793.7 1517.93  4856.8 1517.62  4955.7 1513.11
  4987.8  1505.5  4993.4 1505.23    5000 1501.95 5011.28 1498.94 5019.05  1498.6
 5020.22 1498.96  5022.1 1502.52  5044.4 1512.51  5061.6  1513.3  5492.2  1513.3
  5598.4 1516.73  5633.7 1521.75  5656.4 1528.01  5701.8  1533.6  5718.9 1537.46
  5747.1 1539.96  5764.2 1543.47    5798 1553.27  5815.1 1555.11  5870.6 1557.55
#Mann= 7 ,-1 , 0
  4221.1    .035       0  4283.6     .07       0  4448.6    .035       0
  4676.8     .07       0  4856.8     .07       0  5012.3     .05       0
  5019.9     .07       0
#XS Ineff= 2 , 0
         4849.15 1520.74 5174.25         1518.33
Permanent Ineff=
       F       F
Bank Sta=5011.28,5020.22
XS Rating Curve= 0 ,0
Exp/Cntr=0.3,0.1

Type RM Length L Ch R = 1 ,7372    ,193,193,193
BEGIN DESCRIPTION:
Mapping XS 9de483c6
END DESCRIPTION:
XS GIS Cut Line= 4
      1988446.86     13913061.38      1988189.92     13912729.79
      1988075.34      13912658.6      1987413.93     13912622.15
#Sta/Elev= 30
  4530.2 1524.64    4543  1523.3  4592.8  1521.9  4671.6 1516.86  4829.1 1515.41
  4835.4 1516.25  4849.9 1514.98  4885.2  1515.8  4928.7 1515.28    4979 1511.86
  5007.3 1505.79  5014.3 1501.96  5018.9 1500.64  5019.4 1500.14  5026.5 1500.64
  5028.5 1500.69  5043.9 1510.78  5087.3 1509.86  5195.1 1511.63  5325.3 1511.75
  5455.5 1509.73  5566.8 1510.19  5595.7 1510.88  5602.5 1512.11  5615.7 1511.15
  5635.8 1516.45  5665.8 1527.82  5685.8 1534.11  5735.9 1543.35    5747  1544.5
#Mann= 5 ,-1 , 0
  4530.2     .07       0  4928.7    .035       0  5018.9     .05       0
  5026.5     .07       0  5566.8     .07       0
#XS Ineff= 3 ,-1
 4765.69 4910.09 1517.06 4910.09 4967.83 1514.17 5261.54    5747 1515.57
Permanent Ineff=
       F       F       F
Bank Sta=5018.9,5026.5
XS Rating Curve= 0 ,0
Exp/Cntr=0.3,0.1

Type RM Length L Ch R = 1 ,7179    ,310,310,310
BEGIN DESCRIPTION:
Mapping XS bfddcf52
END DESCRIPTION:
XS GIS Cut Line= 4
      1988748.91      13912596.1      1988351.38     13912585.69
      1988158.67     13912514.51      1987519.03     13912490.24
#Sta/Elev= 30
  4495.5 1533.83  4523.8 1530.79  4549.4 1525.71  4569.4 1520.52  4609.4 1513.17
  4639.5 1511.66  4697.6 1510.75  4727.7 1510.37  4859.5 1508.89  4912.8 1506.49
  4974.6 1505.99  4993.4 1499.52  4994.2 1498.04  4994.7 1497.54  5003.3 1498.04
  5006.6 1498.63  5023.8 1508.29  5034.6 1507.84  5382.5 1510.24  5452.5 1509.34
  5492.6 1507.29  5572.6 1507.11  5592.6 1508.66  5602.6 1508.18  5612.6 1509.67
  5632.7    1514  5654.4 1520.24  5672.7 1525.95  5689.3 1529.46  5738.7 1536.13
#Mann= 9 ,-1 , 0
  4495.5      .1       0  4523.8     .07       0  4697.6      .1       0
  4727.7     .07       0  4994.2     .05       0  5003.3     .07       0
  5034.6    .035       0  5654.4     .07       0  5689.3    .035       0
#XS Ineff= 3 ,-1
 5379.02  5738.7 1510.46 5025.17 5158.04 1508.46  4495.5 4970.63 1506.57
Permanent Ineff=
       F       F       F
Bank Sta=4994.2,5003.3
XS Rating Curve= 0 ,0
Exp/Cntr=0.3,0.1

Type RM Length L Ch R = 1 ,6869    ,211,211,211
BEGIN DESCRIPTION:
Stream0070 12.0
END DESCRIPTION:
XS GIS Cut Line= 3
      1988624.96       13912375.        1988375.       13912375.
      1987444.91       13912473.
#Sta/Elev= 30
  4754.3 1533.74  4791.5 1528.77  4864.3 1510.73  4890.1  1507.4  4924.3 1505.05
  4944.3 1506.82  4954.3  1505.4  4964.3  1497.5  4974.3 1494.56  4979.7 1494.49
  4980.2 1493.99  4988.9 1494.49  4994.3 1495.66  5001.8 1499.97  5006.8 1499.97
  5012.7 1502.61  5024.4 1505.46  5034.4 1506.18  5050.7 1505.48    5100 1506.06
  5446.7 1509.58  5657.9  1506.2  5698.1 1508.12  5716.6  1512.8  5721.6 1511.53
  5752.7  1519.1  5778.5 1525.89  5788.6  1527.4  5897.2 1536.73  5939.5 1539.23
#Mann= 9 ,-1 , 0
  4754.3      .1       0  4791.5     .07       0  4890.1     .07       0
  4979.7     .05       0  4988.9     .07       0  5012.7     .07       0
    5100    .035       0  5752.7     .07       0  5897.2    .035       0
#XS Ineff= 2 , 0
         4944.06 1506.87 5476.92         1509.16
Permanent Ineff=
       F       F
Bank Sta=4979.7,4988.9
XS Rating Curve= 0 ,0
Exp/Cntr=0.3,0.1

Type RM Length L Ch R = 1 ,6658    ,243,243,243
BEGIN DESCRIPTION:
Stream0070 11.1
END DESCRIPTION:
XS GIS Cut Line= 3
      1988759.01     13912274.45       1988386.7     13912179.51
       1987458.1     13912356.81
#Sta/Elev= 30
  4706.9 1543.08  4744.1 1538.08    4773 1534.39  4865.8 1527.66  4876.2 1525.62
  4889.2 1521.05  4907.1 1518.55  4938.1 1507.99  4979.4 1503.77  4989.7 1499.87
  4995.4 1494.19  4995.9 1493.69  5004.6 1494.19  5020.6 1498.62    5031 1500.14
  5041.3 1503.85  5047.1 1503.98  5153.9 1505.22  5316.8 1504.65  5522.9 1506.96
  5627.1 1506.84  5713.9  1504.4  5755.6 1505.59  5764.8 1505.05  5788.6 1509.05
  5815.7 1515.57  5876.8 1523.09  5897.9 1527.54  5986.1 1530.56  6036.5 1532.33
#Mann= 8 ,-1 , 0
  4706.9     .07       0  4744.1      .1       0  4979.4     .07       0
  4995.4     .05       0  5004.6     .07       0  5047.1    .035       0
  5755.6     .07       0  5986.1    .035       0
#XS Ineff= 2 , 0
         4970.85  1505.1 5523.31          1507.1
Permanent Ineff=
       F       F
Bank Sta=4995.4,5004.6
XS Rating Curve= 0 ,0
Exp/Cntr=0.3,0.1

Type RM Length L Ch R = 1 ,6415    ,378,378,378
BEGIN DESCRIPTION:
Stream0070 11.0
END DESCRIPTION:
XS GIS Cut Line= 5
      1988724.97     13912074.99        1988525.       13911975.
      1988137.67     13911765.97      1987824.54     13911788.18
      1987629.78     13911894.05
#Sta/Elev= 30
  4776.4 1533.41  4812.7 1528.07  4874.2 1508.25  4888.2 1504.91  4918.9 1502.75
  4952.1 1502.42  4969.2 1502.45  4977.6 1501.12    4986 1495.62  4992.6 1493.57
  4993.1 1493.07  5001.8 1493.57  5013.8 1498.49  5045.4  1503.1  5073.8 1502.14
  5111.9 1503.47  5183.2 1500.96  5243.2 1501.35  5308.9 1498.92  5397.7  1499.5
  5438.8  1498.4  5643.4  1500.1    5672 1501.64  5683.4 1503.01  5703.4 1501.58
  5723.5 1504.23  5824.1 1504.49  5862.1 1507.41  5905.8 1507.55  5975.7 1510.21
#Mann= 5 ,-1 , 0
  4776.4      .1       0  4952.1     .07       0  4992.6     .05       0
  5001.8     .07       0    5672     .07       0
Bank Sta=4992.6,5001.8
XS Rating Curve= 0 ,0
Exp/Cntr=0.3,0.1