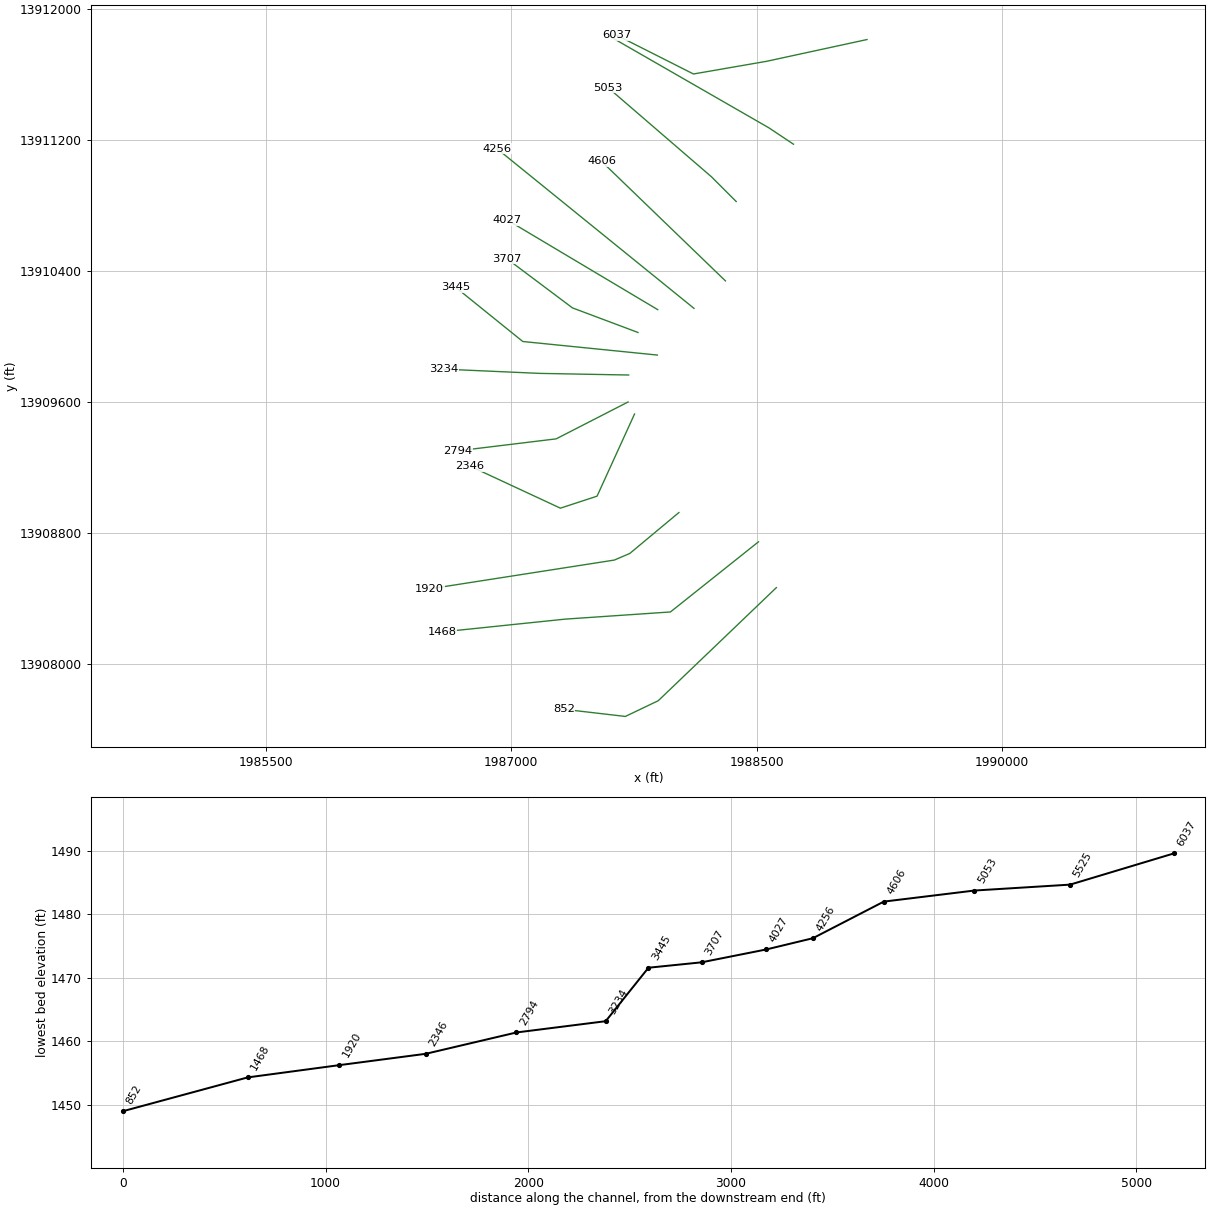
HEC-RAS study Stream0070.prj: Stream0070 Base Level Engineering

--- Stream0070.g01 (geometry) --- (continued)

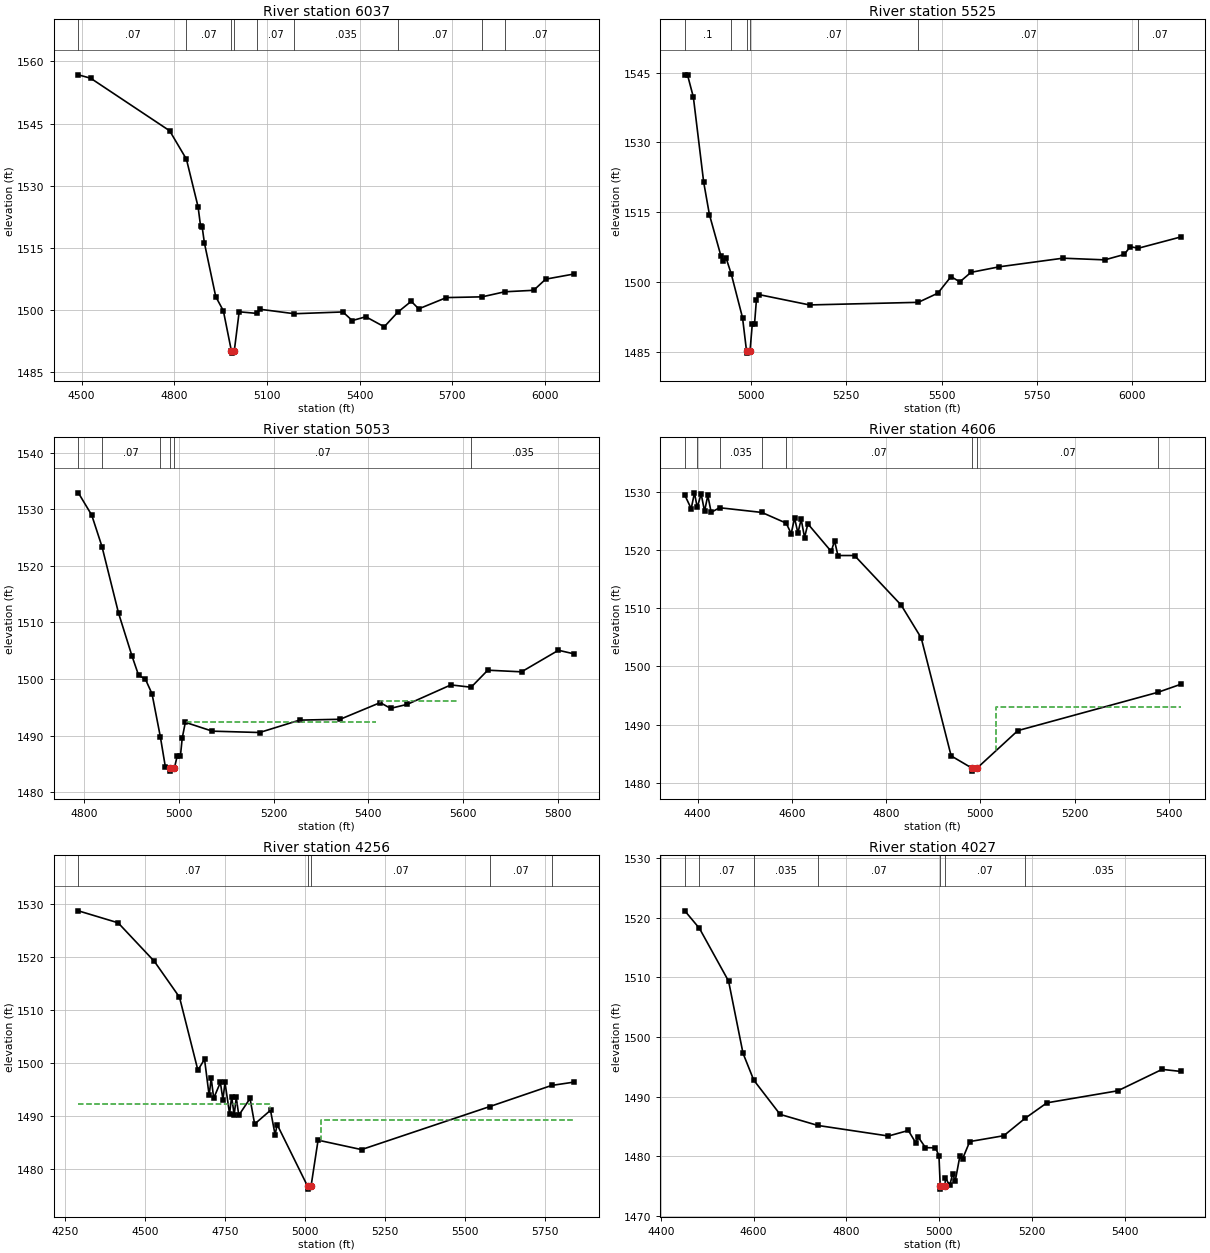
Type RM Length L Ch R = 1 ,6037    ,512,512,512
BEGIN DESCRIPTION:
Stream0070 10.1
END DESCRIPTION:
XS GIS Cut Line= 4
      1989173.98     13911814.46      1988560.87     13911681.55
      1988113.91     13911604.03      1987645.74     13911840.55
#Sta/Elev= 30
  4489.2 1556.76  4529.1 1555.94  4784.9 1543.25  4839.2 1536.39    4877 1524.87
    4885 1520.24  4890.1 1520.07  4897.4 1516.17  4934.2 1503.19  4958.8  1499.8
  4984.9 1490.07  4985.4 1489.57  4994.1 1490.07    5010 1499.55  5067.3 1499.16
  5076.6 1500.17  5188.8 1499.08  5345.8 1499.51  5376.2 1497.43  5420.1 1498.35
  5479.8 1495.93  5523.2 1499.43  5567.1 1502.08  5591.4 1500.26    5681 1502.98
  5796.7 1503.16    5870 1504.38  5963.6 1504.74  6002.5 1507.43  6094.7 1508.68
#Mann= 9 ,-1 , 0
  4489.2     .07       0  4839.2     .07       0  4984.9     .05       0
  4994.1     .07       0  5067.3     .07       0  5188.8    .035       0
  5523.2     .07       0  5796.7    .035       0    5870     .07       0
Bank Sta=4984.9,4994.1
XS Rating Curve= 0 ,0
Exp/Cntr=0.3,0.1

Type RM Length L Ch R = 1 ,5525    ,472,472,472
BEGIN DESCRIPTION:
Stream0070 10.0
END DESCRIPTION:
XS GIS Cut Line= 3
        1988725.       13911175.        1988575.       13911275.
      1987602.19     13911834.28
#Sta/Elev= 30
  4825.6 1544.55  4833.1 1544.41  4848.1 1539.75  4875.2 1521.45  4890.2 1514.49
  4920.2 1505.66  4926.3 1504.55  4933.8  1505.2  4947.7 1501.68  4977.3 1492.26
  4987.7 1485.16  4988.2 1484.66    4997 1485.16  5002.9 1490.98  5008.8 1490.98
  5013.8 1496.19  5019.5 1497.27  5153.2 1495.03  5438.9 1495.59  5490.3 1497.56
  5524.9 1501.13    5548 1499.99  5577.3 1502.04  5651.8 1503.24  5818.8 1505.09
  5928.7 1504.73  5979.8 1505.89  5995.6 1507.56  6017.1 1507.24    6128 1509.65
#Mann= 6 ,-1 , 0
  4825.6      .1       0  4947.7     .07       0  4987.7     .05       0
    4997     .07       0  5438.9     .07       0  6017.1     .07       0
Bank Sta=4987.7,4997
XS Rating Curve= 0 ,0
Exp/Cntr=0.3,0.1

Type RM Length L Ch R = 1 ,5053    ,447,447,447
BEGIN DESCRIPTION:
Stream0070 9.0
END DESCRIPTION:
XS GIS Cut Line= 3
      1988375.02     13910824.98        1988225.       13910975.
      1987592.84     13911519.98
#Sta/Elev= 30
  4787.6 1532.89  4815.9 1528.95  4837.5  1523.4  4872.5 1511.64  4900.8 1504.09
  4914.9 1500.64    4929 1500.01  4943.2 1497.38  4960.9 1489.73  4971.5 1484.39
    4981 1484.23  4981.5 1483.73  4990.3 1484.23  4996.2 1486.36  5003.1 1486.36
  5006.9 1489.55  5013.5 1492.35  5070.5 1490.79  5170.3 1490.55  5254.8 1492.74
  5340.4 1492.89  5424.9 1495.83  5446.8 1494.82  5481.9 1495.52  5574.1 1498.96
  5616.9 1498.55    5652 1501.56  5723.3 1501.27  5801.2 1505.08  5834.4 1504.44
#Mann= 6 ,-1 , 0
  4787.6      .1       0  4837.5     .07       0  4960.9     .07       0
    4981     .05       0  4990.3     .07       0  5616.9    .035       0
#XS Ineff= 3 ,-1
 5423.99 5591.93 1496.06 5014.54 5416.141492.444 5591.93  5834.4  1491.5
Permanent Ineff=
       F       F       F
Bank Sta=4981,4990.3
XS Rating Curve= 0 ,0
Exp/Cntr=0.3,0.1

Type RM Length L Ch R = 1 ,4606    ,350,350,350
BEGIN DESCRIPTION:
Stream0070 8.0
END DESCRIPTION:
XS GIS Cut Line= 2
      1988309.23     13910340.04      1987552.24     13911070.56
#Sta/Elev= 30
    4373  1529.4  4386.6 1527.08  4393.5  1529.8  4399.4 1527.29  4407.7 1529.62
  4414.9 1526.63  4421.8 1529.35    4429 1526.45  4446.8 1527.24  4536.6 1526.43
  4588.1 1524.59  4598.8 1522.78  4605.8 1525.48    4613  1522.9  4619.9 1525.25
  4627.1 1522.12  4634.1 1524.47  4683.7 1519.73  4690.7 1521.56  4697.9 1519.03
  4733.1 1519.03  4832.1 1510.51  4874.6 1504.87  4938.1 1484.61  4982.6 1482.49
  4983.1 1481.99  4992.9 1482.49  5079.6 1488.95  5376.8 1495.53    5425  1496.9
#Mann= 8 ,-1 , 0
    4373    .035       0  4399.4     .07       0  4446.8    .035       0
  4536.6      .1       0  4588.1     .07       0  4982.6     .05       0
  4992.9     .07       0  5376.8    .035       0
#XS Ineff= 2 , 0
                         5033.41         1492.99
Permanent Ineff=
       F       F
Bank Sta=4982.6,4992.9
XS Rating Curve= 0 ,0
Exp/Cntr=0.3,0.1

Type RM Length L Ch R = 1 ,4256    ,229,229,229
BEGIN DESCRIPTION:
Stream0070 7.0
END DESCRIPTION:
XS GIS Cut Line= 2
      1988117.19     13910172.21      1986913.07     13911148.06
#Sta/Elev= 30
  4292.4 1528.75  4416.7 1526.49  4530.2  1519.2  4608.6 1512.45  4666.1 1498.68
  4686.9 1500.74  4701.3  1493.9  4707.7 1497.16  4715.6 1493.39  4736.4 1496.36
  4744.4 1493.12  4750.8 1496.37  4765.2 1490.43  4771.6  1493.7  4779.6 1490.21
    4786 1493.53    4794 1490.16  4829.1 1493.34  4843.5 1488.51  4893.1 1491.11
  4907.5 1486.46  4913.9 1488.41  5009.4 1476.73  5009.9 1476.23  5019.7 1476.73
  5041.8 1485.47  5177.6 1483.69  5578.4 1491.81  5771.9  1495.8  5842.3 1496.43
#Mann= 5 ,-1 , 0
  4292.4     .07       0  5009.4     .05       0  5019.7     .07       0
  5578.4     .07       0  5771.9    .035       0
#XS Ineff= 2 , 0
         4892.31 1492.28 5049.55         1489.21
Permanent Ineff=
       F       F
Bank Sta=5009.4,5019.7
XS Rating Curve= 0 ,0
Exp/Cntr=0.3,0.1

Type RM Length L Ch R = 1 ,4027    ,320,320,320
BEGIN DESCRIPTION:
Mapping XS 2ab31100
END DESCRIPTION:
XS GIS Cut Line= 2
      1987895.59      13910164.4      1986977.52     13910711.46
#Sta/Elev= 30
  4451.7 1521.16  4483.3 1518.21  4546.1 1509.36  4577.2 1497.26  4600.3 1492.76
  4657.1 1487.01  4738.7 1485.15  4890.7 1483.38  4933.5 1484.31  4949.1 1482.29
  4954.9  1483.2  4970.5 1481.43  4991.9  1481.4  4999.5 1480.11  5002.3 1474.97
  5002.8 1474.47  5012.7 1474.97  5013.3 1476.37  5022.8  1475.1  5028.9 1476.99
  5034.7 1475.86  5044.5 1479.96  5050.3 1479.54  5065.9 1482.45  5139.2 1483.43
    5185 1486.34  5232.3 1488.95  5385.1 1490.97  5480.5 1494.56  5520.4 1494.22
#Mann= 7 ,-1 , 0
  4451.7      .1       0  4483.3     .07       0  4600.3    .035       0
  4738.7     .07       0  5002.3     .05       0  5012.7     .07       0
    5185    .035       0
Bank Sta=5002.3,5012.7
XS Rating Curve= 0 ,0
Exp/Cntr=0.3,0.1

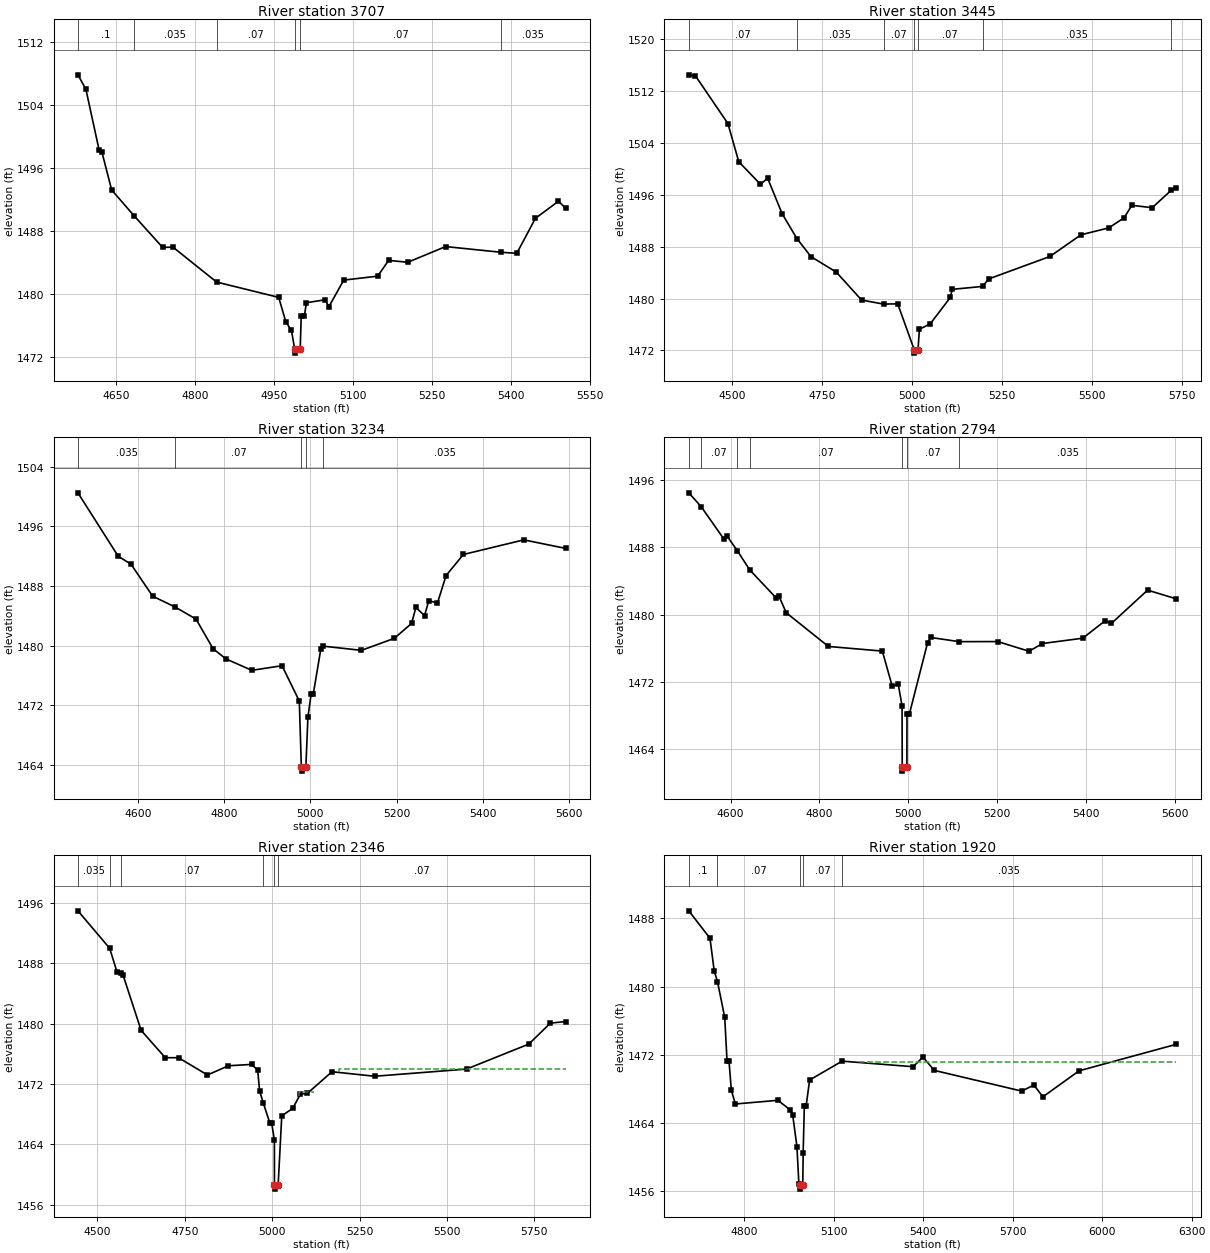
Type RM Length L Ch R = 1 ,3707    ,262,262,262
BEGIN DESCRIPTION:
Stream0070 6.0
END DESCRIPTION:
XS GIS Cut Line= 3
      1987775.03     13910024.99        1987375.       13910175.
      1986975.03     13910474.98
#Sta/Elev= 30
  4577.1 1507.88  4592.3 1506.03  4617.2 1498.36  4622.5  1498.1  4641.2 1493.22
    4684 1489.92  4738.2  1485.9  4757.8 1485.94  4840.8 1481.49  4958.9 1479.54
  4972.3 1476.43    4983 1475.35  4989.3 1472.94  4989.8 1472.44  4999.7 1472.94
  5001.7 1477.13  5007.5 1477.13  5011.6 1478.86    5047 1479.23  5054.3 1478.35
  5082.5 1481.74    5147 1482.24  5167.9 1484.25  5204.3 1484.01  5276.2 1486.01
  5382.1 1485.28  5411.6 1485.15    5447 1489.61  5490.8 1491.78  5504.3  1490.9
#Mann= 6 ,-1 , 0
  4577.1      .1       0    4684    .035       0  4840.8     .07       0
  4989.3     .05       0  4999.7     .07       0  5382.1    .035       0
Bank Sta=4989.3,4999.7
XS Rating Curve= 0 ,0
Exp/Cntr=0.3,0.1

Type RM Length L Ch R = 1 ,3445    ,211,211,211
BEGIN DESCRIPTION:
Strem0070 5.1
END DESCRIPTION:
XS GIS Cut Line= 3
       1987893.4     13909886.99      1987071.19     13909969.82
      1986658.47     13910303.02
#Sta/Elev= 30
  4378.5 1514.44    4397 1514.29  4487.4 1506.93  4517.6 1501.05  4577.9 1497.59
    4598 1498.51  4638.2 1493.05  4679.3 1489.23  4718.6 1486.44    4789 1484.06
  4859.3 1479.76  4920.5 1479.14  4959.8 1479.18  5005.9 1472.09  5006.4 1471.59
  5016.3 1472.09  5020.1 1475.26  5050.3  1476.1  5106.2 1480.16  5111.3 1481.41
  5195.9 1481.86  5212.8 1483.01  5383.3 1486.47  5469.6 1489.81    5547 1490.87
  5589.6 1492.42  5611.2 1494.35  5667.9 1493.98  5720.1 1496.63  5735.3 1497.07
#Mann= 7 ,-1 , 0
  4378.5     .07       0  4679.3    .035       0  4920.5     .07       0
  5005.9     .05       0  5016.3     .07       0  5195.9    .035       0
  5720.1     .07       0
Bank Sta=5005.9,5016.3
XS Rating Curve= 0 ,0
Exp/Cntr=0.3,0.1

Type RM Length L Ch R = 1 ,3234    ,440,440,440
BEGIN DESCRIPTION:
Stream0070 5.0
END DESCRIPTION:
XS GIS Cut Line= 3
      1987718.14     13909765.08        1987175.       13909775.
      1986588.31     13909801.01
#Sta/Elev= 30
    4461 1500.51  4554.2 1492.02  4584.2 1490.93  4634.2 1486.65    4687 1485.17
  4734.8 1483.57  4774.2 1479.61  4804.2 1478.23  4864.2  1476.7  4934.2 1477.32
  4974.2 1472.58    4979 1463.68  4979.5 1463.18  4989.4 1463.68  4994.2 1470.41
  5001.7 1473.55  5006.7 1473.55  5024.3 1479.62  5030.1 1479.94  5118.2 1479.38
  5194.4 1480.99  5234.5 1482.99  5244.5 1485.13  5264.5 1484.04  5274.5 1486.05
  5294.5 1485.72  5314.5 1489.42  5354.6 1492.24  5494.7  1494.2  5591.5 1493.06
#Mann= 5 ,-1 , 0
    4461    .035       0    4687     .07       0    4979     .05       0
  4989.4     .07       0  5030.1    .035       0
Bank Sta=4979,4989.4
XS Rating Curve= 0 ,0
Exp/Cntr=0.3,0.1

Type RM Length L Ch R = 1 ,2794    ,448,448,448
BEGIN DESCRIPTION:
Stream0070 4.0
END DESCRIPTION:
XS GIS Cut Line= 3
      1987714.59     13909600.36        1987275.       13909375.
       1986675.6     13909302.18
#Sta/Elev= 30
    4506 1494.47  4533.8 1492.83  4584.2 1489.04  4592.1 1489.34  4615.3 1487.59
  4642.8 1485.34  4703.1 1481.96  4708.8 1482.21  4725.3 1480.23  4820.2 1476.22
  4941.7 1475.67  4963.9 1471.51  4977.5 1471.74  4986.1 1469.17  4986.5 1461.91
    4987 1461.41    4997 1461.91  4997.2 1468.18  5002.5 1468.18  5043.4 1476.62
  5050.4 1477.29  5114.7 1476.79  5201.5  1476.8    5272 1475.65  5302.2 1476.57
  5392.9  1477.2  5443.2 1479.27  5457.2 1478.95  5538.9 1482.91  5603.8 1481.87
#Mann= 7 ,-1 , 0
    4506    .035       0  4533.8     .07       0  4615.3      .1       0
  4642.8     .07       0  4986.5     .05       0    4997     .07       0
  5114.7    .035       0
Bank Sta=4986.5,4997
XS Rating Curve= 0 ,0
Exp/Cntr=0.3,0.1

Type RM Length L Ch R = 1 ,2346    ,426,426,426
BEGIN DESCRIPTION:
Stream0070 3.0
END DESCRIPTION:
XS GIS Cut Line= 4
      1987753.93     13909526.85        1987525.       13909025.
      1987300.99     13908951.65      1986749.83     13909208.08
#Sta/Elev= 30
  4444.1 1494.96  4534.8    1490    4556 1486.85  4566.3 1486.69  4573.3 1486.43
  4624.9 1479.11    4694 1475.48  4731.9 1475.48  4814.7 1473.19  4874.8 1474.41
  4940.9 1474.59  4958.4 1473.85  4963.9 1471.07  4974.9 1469.41    4993 1466.84
  4998.3 1466.84  5006.2 1464.57  5006.4 1458.55  5006.9 1458.05  5016.9 1458.55
  5027.3 1467.78  5058.8 1468.76  5080.6 1470.65  5100.9 1470.76  5170.9 1473.62
  5293.1 1473.02  5555.9 1473.97  5734.3 1477.29  5795.7 1480.06  5839.3 1480.28
#Mann= 6 ,-1 , 0
  4444.1    .035       0  4534.8      .1       0  4566.3     .07       0
  4974.9     .07       0  5006.4     .05       0  5016.9     .07       0
#XS Ineff= 3 ,-1
  4444.1 4933.87 1474.48 5191.21  5839.3    1474 5077.72 5120.88 1470.89
Permanent Ineff=
       F       F       F
Bank Sta=5006.4,5016.9
XS Rating Curve= 0 ,0
Exp/Cntr=0.3,0.1

Type RM Length L Ch R = 1 ,1920    ,452,452,452
BEGIN DESCRIPTION:
Stream0070 2.0
END DESCRIPTION:
XS GIS Cut Line= 4
      1988025.01     13908925.01        1987725.       13908675.
      1987630.13     13908634.55      1986502.72     13908458.74
#Sta/Elev= 30
  4614.3 1488.89  4685.3 1485.68  4699.6 1481.83  4710.5 1480.59  4734.7 1476.41
  4742.5 1471.32    4749 1471.34  4756.9 1467.85  4770.5 1466.25  4913.1 1466.68
  4954.7 1465.55  4962.5    1465  4976.8 1461.26  4983.4 1456.83  4985.9 1456.77
  4986.4 1456.27  4996.4 1456.77  4997.7 1460.54  5001.6 1465.99  5007.5 1465.99
  5019.4 1469.06  5128.2 1471.27  5366.2 1470.62  5399.4 1471.75    5437 1470.19
  5730.5 1467.76    5771 1468.47  5801.4 1467.09  5922.8 1470.14    6249 1473.25
#Mann= 5 ,-1 , 0
  4614.3      .1       0  4710.5     .07       0  4985.9     .05       0
  4996.4     .07       0  5128.2    .035       0
#XS Ineff= 2 , 0
                         5184.42         1471.21
Permanent Ineff=
       F       F
Bank Sta=4985.9,4996.4
XS Rating Curve= 0 ,0
Exp/Cntr=0.3,0.1

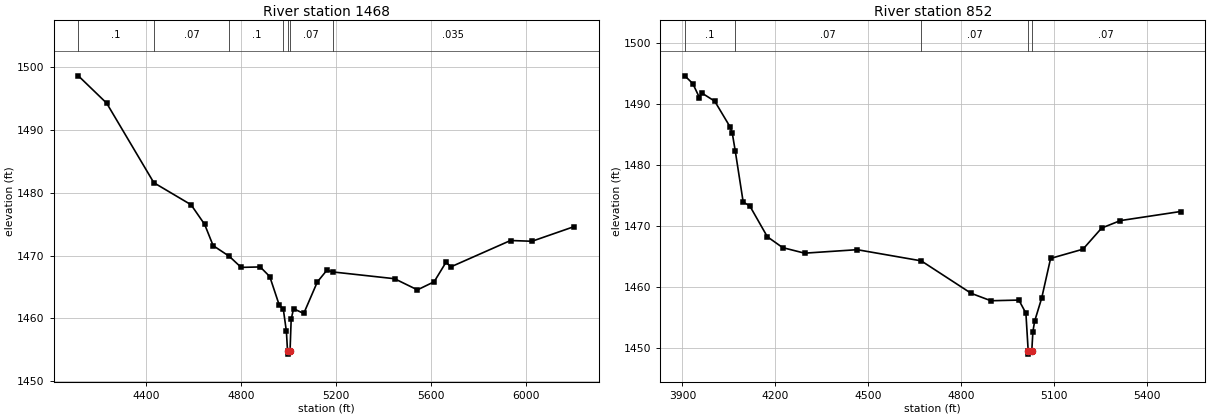
Type RM Length L Ch R = 1 ,1468    ,616,616,616
BEGIN DESCRIPTION:
Stream0070 1.1
END DESCRIPTION:
XS GIS Cut Line= 4
      1988510.98     13908746.01       1987973.3     13908317.61
      1987330.67     13908273.89      1986578.41     13908195.72
#Sta/Elev= 30
  4113.7 1498.55  4232.9 1494.21  4431.6 1481.57  4588.4 1478.07  4645.6 1474.95
  4681.3 1471.58  4749.3 1469.88  4799.3 1468.12  4879.7 1468.19  4919.8 1466.66
  4959.8 1462.12  4976.6 1461.56  4989.9 1457.94  4994.6 1454.84  4995.1 1454.34
  5005.2 1454.84    5010 1459.88    5020 1461.55  5062.9  1460.8  5120.2 1465.81
  5160.3 1467.67  5184.3  1467.4  5445.3 1466.32  5541.5 1464.55  5611.9 1465.83
  5662.1 1468.94  5682.2  1468.2  5933.6 1472.39  6024.1 1472.27  6201.6  1474.6
#Mann= 7 ,-1 , 0
  4113.7      .1       0  4431.6     .07       0  4749.3      .1       0
  4976.6     .07       0  4994.6     .05       0  5005.2     .07       0
  5184.3    .035       0
#XS Ineff= 2 , 0
                         5183.82         1467.27
Permanent Ineff=
       F       F
Bank Sta=4994.6,5005.2
XS Rating Curve= 0 ,0
Exp/Cntr=0.3,0.1

Type RM Length L Ch R = 1 ,852     ,0,0,0
BEGIN DESCRIPTION:
Stream0070 1.0
END DESCRIPTION:
XS GIS Cut Line= 4
       1988620.3     13908466.24      1987898.98     13907775.52
      1987697.89     13907679.35      1987321.92     13907723.06
#Sta/Elev= 30
  3907.7 1494.64  3933.5 1493.37  3954.9 1491.07  3961.8 1491.85  4004.3 1490.48
  4053.6 1486.29  4060.9 1485.25  4070.8 1482.24  4096.1 1473.95  4117.5 1473.31
  4174.1 1468.26  4223.5 1466.48  4294.2 1465.57    4464 1466.14  4670.7 1464.31
  4831.7 1458.99  4895.5 1457.77  4985.8 1457.88  5008.5 1455.73  5015.9 1449.52
  5016.4 1449.02  5027.4 1449.52  5031.1 1452.72  5036.7 1454.42  5059.4  1458.2
  5088.2 1464.71  5192.6 1466.22    5253 1469.69  5313.4 1470.91  5507.8  1472.4
#Mann= 5 ,-1 , 0
  3907.7      .1       0  4070.8     .07       0  4670.7     .07       0
  5015.9     .05       0  5027.4     .07       0
Bank Sta=5015.9,5027.4
XS Rating Curve= 0 ,0
Exp/Cntr=0.3,0.1

Chan Stop Cuts=-1
Use User Specified Reach Order=0
Composite Channel Slope=5