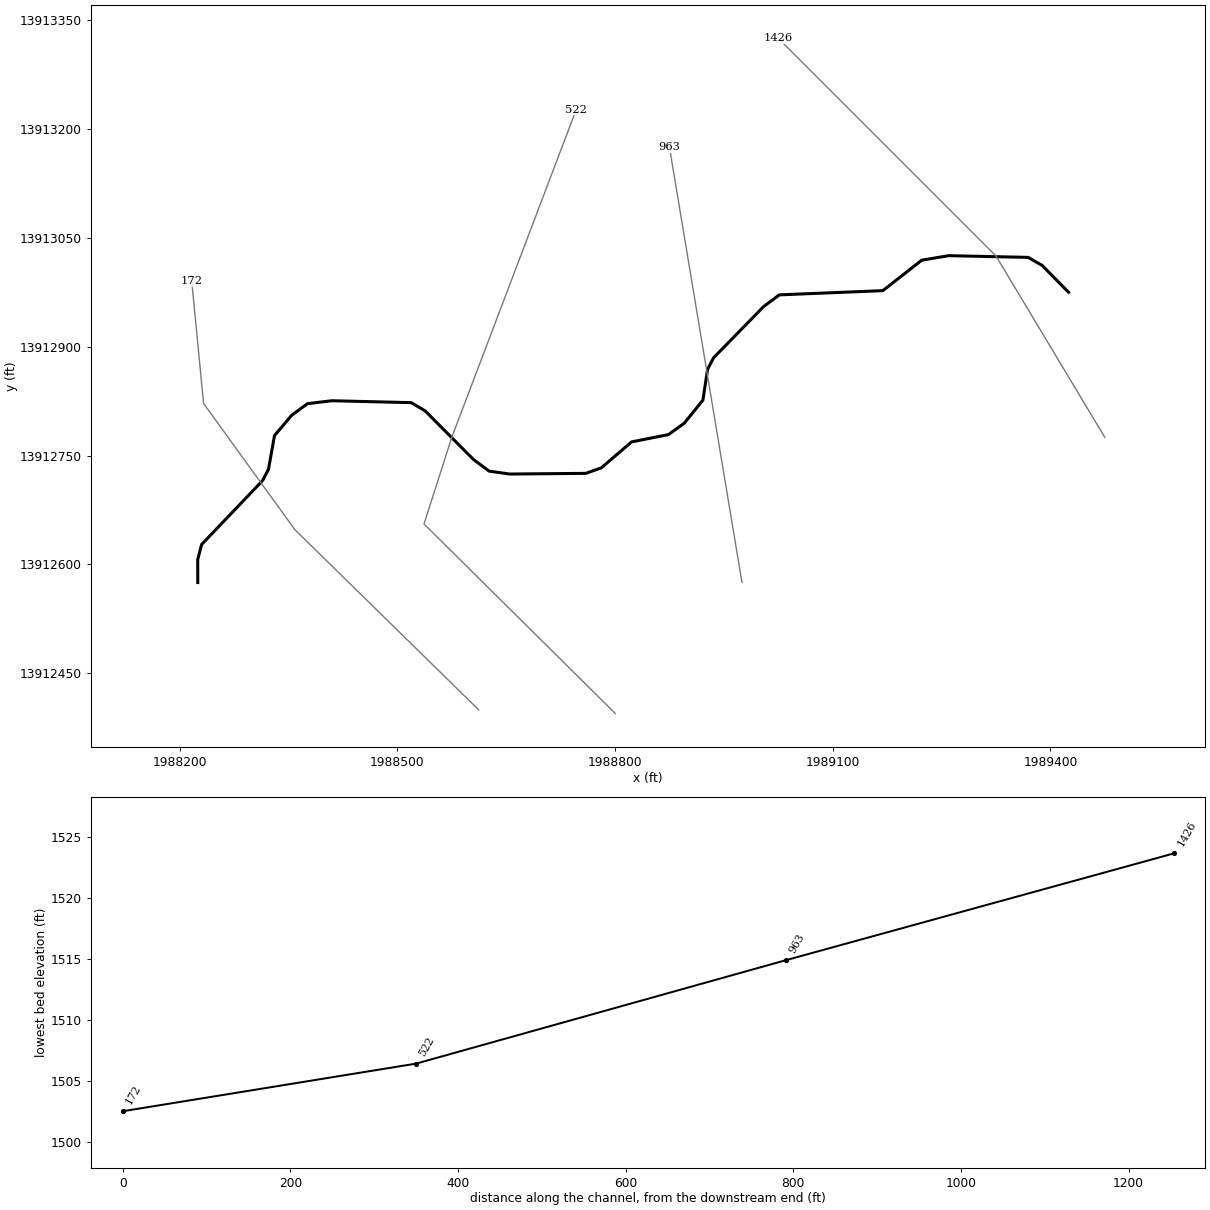
--- Stream0071.prj (project) ---

Proj Title=Stream0071 Base Level Engineering
Current Plan=p01
Default Exp/Contr=0.3,0.1
English Units
Geom File=g01
Flow File=f01
Plan File=p01
BEGIN DESCRIPTION:
Stream0071
END DESCRIPTION:

--- Stream0071.p01 (plan) ---

Plan Title=Multiple Run
Short Identifier=Multiple
Geom File=g01
Flow File=f01
Subcritical Flow
K Sum by GR= 0
Std Step Tol= 0.01
Critical Tol= 0.01
Num of Std Step Trials= 20
Max Error Tol= 0.3
Flow Tol Ratio= 0.001
Split Flow NTrial= 30
Split Flow Tol= 0.02
Split Flow Ratio= 0.02
Log Output Level= 0
Friction Slope Method= 1
Unsteady Friction Slope Method= 2
Unsteady Bridges Friction Slope Method= 1
Parabolic Critical Depth
Global Vel Dist=  1 , 1 , 1
Global Log Level= 0
CheckData=True
Encroach Param= -1, 0, 0, 0
BEGIN DESCRIPTION:
Multiple Run
END DESCRIPTION:

--- Stream0071.f01 (steady flow) ---

Flow Title=Multiple
Number of Profiles=7
Profile Names=10-year,25-year,50-year,1pct_min,100-year,1pct_plu,500-year
River Rch & RM= Stream0071,Reach-1,1426
     724    1214    1677    1126    2246    4481    3991
Boundary for River Rch & Prof#=Stream0071,Reach-1,1
Up Type=0
Dn Type=3
Dn Slope=0.005
Boundary for River Rch & Prof#=Stream0071,Reach-1,2
Up Type=0
Dn Type=3
Dn Slope=0.005
Boundary for River Rch & Prof#=Stream0071,Reach-1,3
Up Type=0
Dn Type=3
Dn Slope=0.005
Boundary for River Rch & Prof#=Stream0071,Reach-1,4
Up Type=0
Dn Type=3
Dn Slope=0.005
Boundary for River Rch & Prof#=Stream0071,Reach-1,5
Up Type=0
Dn Type=3
Dn Slope=0.005
Boundary for River Rch & Prof#=Stream0071,Reach-1,6
Up Type=0
Dn Type=3
Dn Slope=0.005
Boundary for River Rch & Prof#=Stream0071,Reach-1,7
Up Type=0
Dn Type=3
Dn Slope=0.005

--- Stream0071.g01 (geometry) ---

Geom Title=Existing Conditions

River Reach=Stream0071,Reach-1
Reach XY= 30
      1989425.00     13912975.00      1989388.50     13913012.09
      1989369.21     13913023.12      1989259.83     13913025.47
      1989222.67     13913019.26      1989169.06     13912977.27
      1989026.46     13912971.46      1989004.80     13912955.41
      1988935.78     13912884.69      1988927.55     13912868.92
      1988921.11     13912826.43      1988895.47     13912794.62
      1988873.58     13912778.86      1988822.85     13912768.85
      1988781.08     13912733.09      1988759.78     13912725.49
      1988654.84     13912724.54      1988626.47     13912728.54
      1988604.86     13912744.65      1988538.30     13912811.60
      1988519.14     13912822.94      1988409.76     13912825.56
      1988376.25     13912821.56      1988354.45     13912805.56
      1988330.74     13912777.58      1988322.44     13912731.09
      1988314.21     13912715.34      1988230.33     13912627.51
      1988224.93     13912606.88      1988225.00     13912575.00

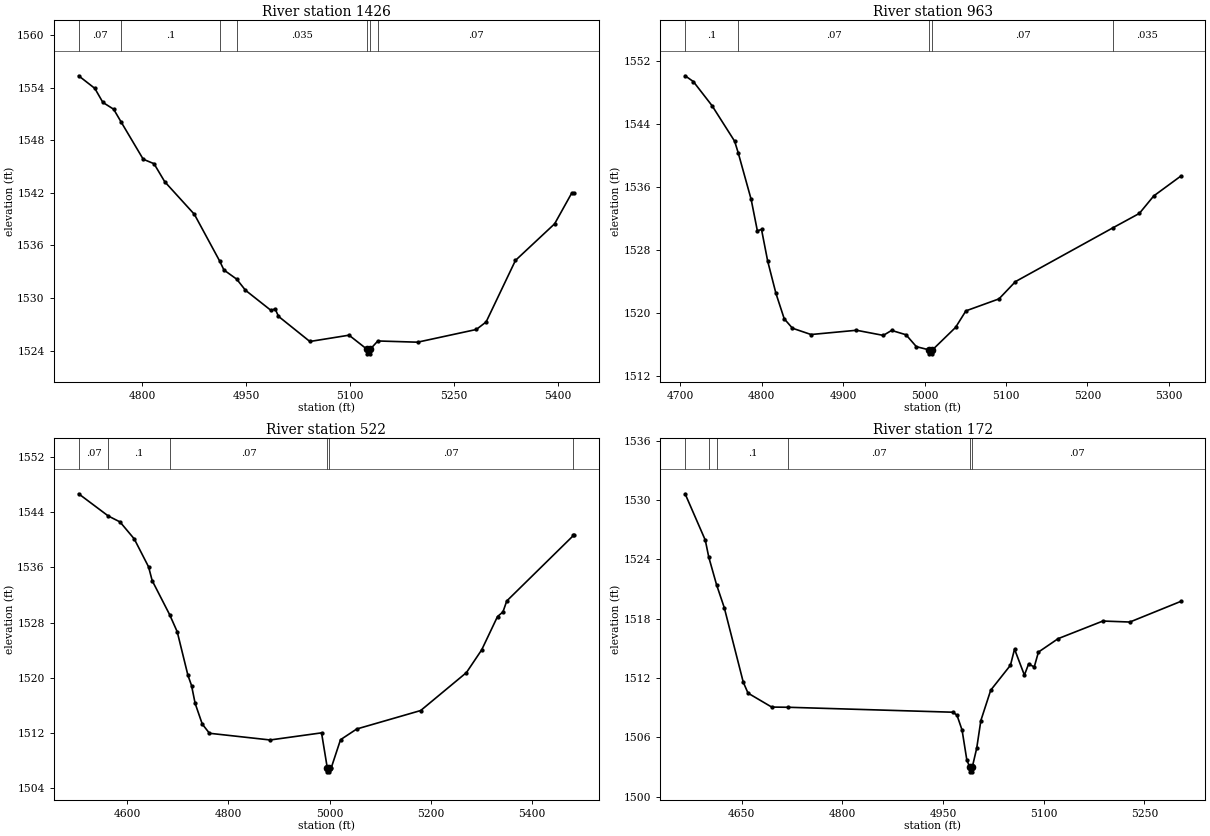
Type RM Length L Ch R = 1,1426,463,463,463
BEGIN DESCRIPTION:
Stream0071 3.0
END DESCRIPTION:
XS GIS Cut Line= 3
      1989475.01     13912774.98      1989325.00     13913025.00
      1989025.03     13913324.97
#Sta/Elev= 30
  4707.8 1555.37  4731.2 1553.93  4742.8 1552.33  4758.4 1551.55  4768.9 1550.13
  4801.1 1545.84  4816.7 1545.33  4832.2 1543.27  4875.0 1539.55  4911.7 1534.19
  4917.7 1533.19  4936.1 1532.15  4948.8 1530.88  4985.8 1528.57  4991.6 1528.76
  4996.5 1527.90  5041.8 1525.03  5098.4 1525.75  5124.7 1524.12  5124.9 1523.62
  5128.4 1523.62  5128.7 1524.12  5140.0 1525.09  5197.4 1524.95  5282.2 1526.40
  5296.4 1527.26  5338.8 1534.29  5395.4 1538.47  5420.1 1541.98  5423.6 1541.98
#Mann=7,-1,0
  4707.8    0.07       0  4768.9     0.1       0  4911.7    0.07       0
  4936.1   0.035       0  5124.7   0.035       0  5128.7   0.035       0
  5140.0    0.07       0
Bank Sta=5124.7,5128.7
Exp/Cntr=0.3,0.1

Type RM Length L Ch R = 1,963,441,441,441
BEGIN DESCRIPTION:
Stream0071 2.0
END DESCRIPTION:
XS GIS Cut Line= 3
      1988975.00     13912574.99      1988925.00     13912875.00
      1988875.00     13913175.01
#Sta/Elev= 30
  4706.1 1550.14  4716.2 1549.41  4739.1 1546.36  4766.9 1541.84  4771.3 1540.37
  4787.2 1534.45  4794.8 1530.48  4799.9 1530.65  4807.5 1526.62  4817.6 1522.54
  4827.8 1519.31  4837.9 1518.12  4860.7 1517.32  4916.5 1517.86  4949.4 1517.21
  4959.6 1517.84  4977.3 1517.29  4990.0 1515.78  5005.7 1515.37  5006.0 1514.87
  5009.5 1514.87  5009.7 1515.37  5038.1 1518.22  5050.8 1520.32  5091.4 1521.84
  5111.6 1524.03  5231.7 1530.88  5263.7 1532.68  5281.4 1534.90  5314.4 1537.40
#Mann=5,-1,0
  4706.1     0.1       0  4771.3    0.07       0  5005.7    0.05       0
  5009.7    0.07       0  5231.7   0.035       0
Bank Sta=5005.7,5009.7
Exp/Cntr=0.3,0.1

Type RM Length L Ch R = 1,522,350,350,350
BEGIN DESCRIPTION:
Stream0071 1.0
END DESCRIPTION:
XS GIS Cut Line= 4
      1988800.23     13912394.73      1988536.78     13912655.72
      1988575.00     13912775.00      1988746.47     13913226.65
#Sta/Elev= 30
  4503.9 1546.63  4562.6 1543.41  4585.6 1542.56  4613.8 1540.10  4642.1 1536.06
  4649.2 1534.07  4683.6 1529.16  4698.7 1526.67  4719.9 1520.36  4727.0 1518.89
  4734.1 1516.31  4748.2 1513.31  4762.4 1511.98  4882.3 1511.01  4983.9 1512.04
  4995.4 1506.90  4995.6 1506.40  4999.1 1506.40  4999.4 1506.90  5002.7 1506.90
  5021.4 1511.05  5053.5 1512.60  5179.8 1515.27  5270.2 1520.76  5300.3 1524.04
  5331.6 1528.87  5342.3 1529.53  5349.9 1531.12  5481.7 1540.60  5483.1 1540.60
#Mann=6,-1,0
  4503.9    0.07       0  4562.6     0.1       0  4683.6    0.07       0
  4995.4    0.05       0  4999.4    0.07       0  5481.7   0.035       0
Bank Sta=4995.4,4999.4
Exp/Cntr=0.3,0.1

Type RM Length L Ch R = 1,172,0,0,0
BEGIN DESCRIPTION:
Stream0071 0.0
END DESCRIPTION:
XS GIS Cut Line= 4
      1988612.14     13912399.57      1988358.67     13912648.07
      1988233.02     13912821.73      1988216.66     13912990.32
#Sta/Elev= 30
  4565.4 1530.62  4595.5 1525.93  4600.7 1524.21  4612.3 1521.42  4623.8 1519.10
  4652.1 1511.57  4659.2 1510.46  4694.5 1509.05  4719.1 1509.03  4964.5 1508.53
  4970.7 1508.23  4978.3 1506.72  4985.4 1503.69  4989.6 1503.00  4989.8 1502.50
  4993.3 1502.50  4993.6 1503.00  5000.1 1504.89  5006.3 1507.69  5021.0 1510.76
  5050.4 1513.28  5056.5 1514.91  5071.2 1512.28  5077.4 1513.40  5085.9 1513.11
  5092.1 1514.61  5121.5 1515.97  5188.2 1517.75  5228.4 1517.65  5304.1 1519.73
#Mann=6,-1,0
  4565.4     0.1       0  4600.7    0.07       0  4612.3     0.1       0
  4719.1    0.07       0  4989.6    0.05       0  4993.6    0.07       0
Bank Sta=4989.6,4993.6
Exp/Cntr=0.3,0.1

Chan Stop Cuts=-1