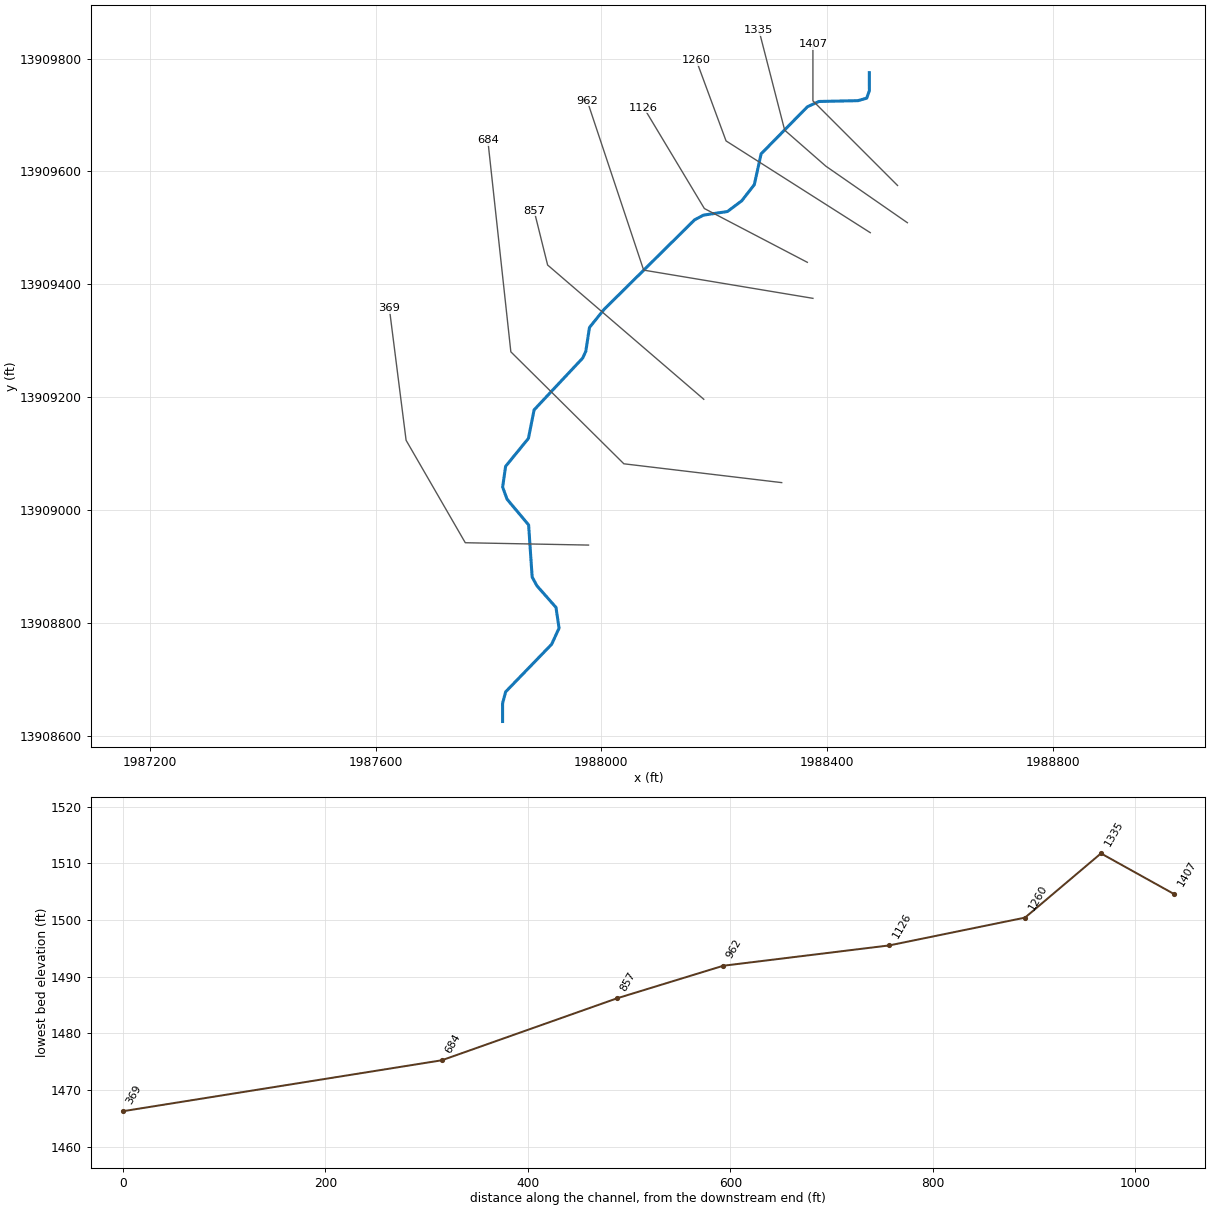
--- Stream0072.prj (project) ---

Proj Title=Stream0072 Base Level Engineering
Current Plan=p01
Default Exp/Contr=0.3,0.1
English Units
Geom File=g01
Flow File=f01
Plan File=p01
Y Axis Title=Elevation
X Axis Title(PF)=Main Channel Distance
X Axis Title(XS)=Station
BEGIN DESCRIPTION:
Stream0072
END DESCRIPTION:
DSS Export Rating Curves= 0
DSS Export Rating Curve Sorted= 0
DSS Export Volume Flow Curves= 0
DXF OffsetX= 0
DXF OffsetY= 0
DXF ScaleX= 1
DXF ScaleY= 10

--- Stream0072.p01 (plan) ---

Plan Title=Multiple Run
Short Identifier=Multiple
Geom File=g01
Flow File=f01
Subcritical Flow
K Sum by GR= 0
Std Step Tol= 0.01
Critical Tol= 0.01
Num of Std Step Trials= 20
Max Error Tol= 0.3
Flow Tol Ratio= 0.001
Split Flow NTrial= 30
Split Flow Tol= 0.02
Split Flow Ratio= 0.02
Log Output Level= 0
Friction Slope Method= 1
Unsteady Friction Slope Method= 2
Unsteady Bridges Friction Slope Method= 1
Parabolic Critical Depth
Global Vel Dist=  1 , 1 , 1
Global Log Level= 0
CheckData=True
Encroach Param= -1, 0, 0, 0
BEGIN DESCRIPTION:
Multiple Run
END DESCRIPTION:

--- Stream0072.f01 (steady flow) ---

Flow Title=Multiple
Number of Profiles=7
Profile Names=10-year,25-year,50-year,1pct_min,100-year,1pct_plu,500-year
River Rch & RM= Stream0072,Reach-1,1407
      86     121     148      89     178     356     252
Boundary for River Rch & Prof#=Stream0072,Reach-1,1
Up Type=0
Dn Type=3
Dn Slope=0.005
Boundary for River Rch & Prof#=Stream0072,Reach-1,2
Up Type=0
Dn Type=3
Dn Slope=0.005
Boundary for River Rch & Prof#=Stream0072,Reach-1,3
Up Type=0
Dn Type=3
Dn Slope=0.005
Boundary for River Rch & Prof#=Stream0072,Reach-1,4
Up Type=0
Dn Type=3
Dn Slope=0.005
Boundary for River Rch & Prof#=Stream0072,Reach-1,5
Up Type=0
Dn Type=3
Dn Slope=0.005
Boundary for River Rch & Prof#=Stream0072,Reach-1,6
Up Type=0
Dn Type=3
Dn Slope=0.005
Boundary for River Rch & Prof#=Stream0072,Reach-1,7
Up Type=0
Dn Type=3
Dn Slope=0.005

--- Stream0072.g01 (geometry) ---

Geom Title=Existing Conditions
Program Version=4.10

River Reach=Stream0072      ,Reach-1
Reach XY= 30
        1988475.       13909775.      1988475.08      13909743.1
      1988470.32     13909729.75       1988454.8     13909725.34
      1988385.52      13909723.9      1988365.21     13909714.51
      1988283.16     13909631.05      1988271.11     13909576.43
      1988248.84     13909547.86      1988223.57     13909528.89
      1988181.09     13909522.45      1988165.34     13909514.21
      1988004.62     13909355.16      1987978.97     13909323.35
      1987972.46     13909281.05      1987966.82     13909268.96
      1987880.84     13909177.29      1987870.75     13909126.74
      1987830.34      13909077.2      1987825.09      13909040.4
      1987832.81     13909019.08      1987871.11     13908973.42
      1987877.38     13908880.97      1987885.95     13908865.35
      1987919.65     13908827.17      1987925.05     13908790.34
      1987911.88     13908761.79      1987830.33     13908677.51
      1987824.93     13908656.88        1987825.       13908625.

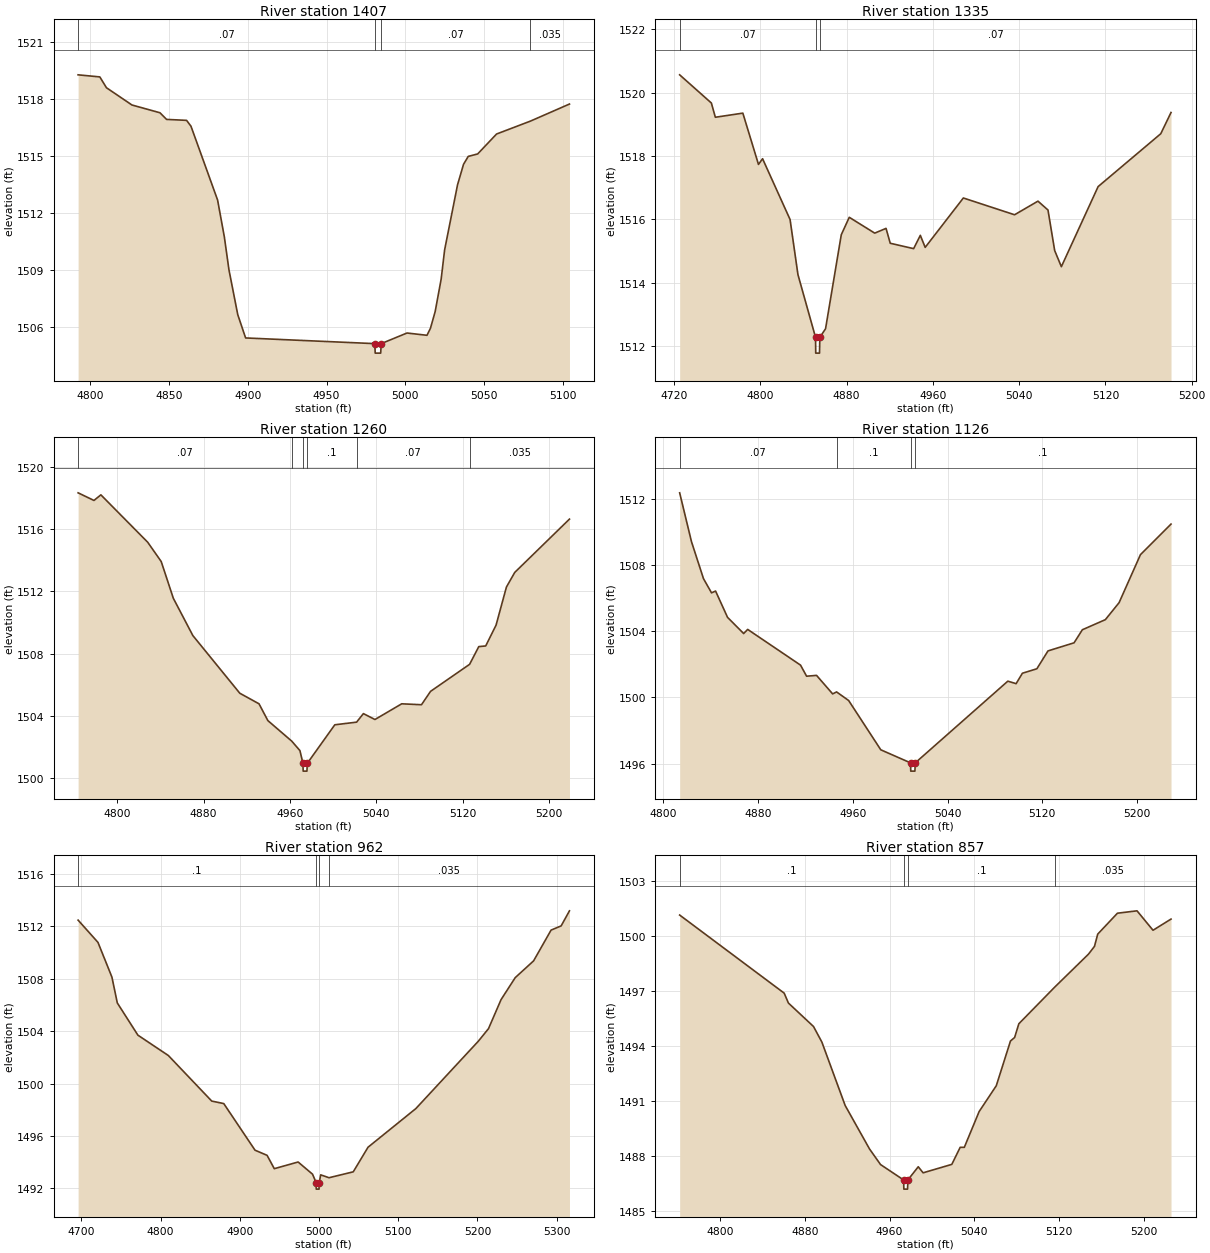
Type RM Length L Ch R = 1 ,1407    ,72,72,72
BEGIN DESCRIPTION:
Stream0072 3.0
END DESCRIPTION:
XS GIS Cut Line= 3
      1988524.99     13909575.01        1988375.       13909725.
        1988375.     13909824.98
#Sta/Elev= 30
  4792.2 1519.29    4806 1519.18  4810.2 1518.61  4826.4  1517.7  4844.2 1517.29
  4848.4 1516.94  4861.1 1516.89  4863.9 1516.58  4880.8 1512.69  4885.1 1510.74
    4888 1509.02  4893.6 1506.65  4898.6 1505.42  4980.7 1505.12  4980.9 1504.62
  4984.4 1504.62  4984.7 1505.12  5001.1 1505.68  5013.8 1505.56    5016 1505.93
    5019 1506.81  5022.8 1508.52    5025 1510.06  5033.2 1513.49    5037 1514.57
    5040 1514.99    5046 1515.12    5058 1516.17  5079.5 1516.85  5104.3 1517.75
#Mann= 4 ,-1 , 0
  4792.2     .07       0  4980.7     .05       0  4984.7     .07       0
  5079.5    .035       0
Bank Sta=4980.7,4984.7
XS Rating Curve= 0 ,0
Exp/Cntr=0.3,0.1

Type RM Length L Ch R = 1 ,1335    ,75,75,75
BEGIN DESCRIPTION:
Stream0072 5.0
END DESCRIPTION:
XS GIS Cut Line= 4
       1988542.4     13909509.02      1988397.84     13909609.29
      1988324.93     13909673.09      1988279.35      13909850.2
#Sta/Elev= 30
  4725.1 1520.56  4754.5 1519.67  4758.2 1519.22  4783.7 1519.35  4798.2 1517.73
    4802 1517.91  4827.5 1515.99  4834.8 1514.25  4851.1 1512.27  4851.3 1511.77
  4854.8 1511.77  4855.1 1512.27  4860.4 1512.54    4875 1515.51  4882.4 1516.06
    4906 1515.56  4916.5 1515.71  4920.4 1515.24  4942.1 1515.07  4948.3 1515.49
  4952.8 1515.11  4988.2 1516.67  5035.7 1516.14  5057.4 1516.57  5066.7 1516.29
  5072.9 1515.01  5079.1  1514.5  5113.2 1517.03  5171.3  1518.7  5180.8 1519.37
#Mann= 3 ,-1 , 0
  4725.1     .07       0  4851.1     .05       0  4855.1     .07       0
Bank Sta=4851.1,4855.1
XS Rating Curve= 0 ,0
Exp/Cntr=0.3,0.1

Type RM Length L Ch R = 1 ,1260    ,134,134,134
BEGIN DESCRIPTION:
Mapping XS 5d4a4c5c
END DESCRIPTION:
XS GIS Cut Line= 3
      1988476.67     13909491.36      1988221.03     13909654.01
      1988168.34     13909796.81
#Sta/Elev= 30
  4763.8 1518.34  4778.5 1517.85  4784.9 1518.21  4828.3 1515.16  4840.8 1513.92
    4852 1511.56  4870.1 1509.16  4913.6 1505.45  4931.4 1504.77  4939.6 1503.69
  4961.7 1502.37  4969.3 1501.76  4972.1 1500.94  4972.3 1500.44  4975.8 1500.44
  4976.1 1500.94  5001.6 1503.42  5021.8 1503.59  5028.1 1504.14  5038.8 1503.76
  5063.6 1504.77  5081.9 1504.71  5090.3 1505.57  5126.5 1507.31    5135 1508.45
  5141.4 1508.49    5151 1509.83  5160.6 1512.28  5168.3 1513.22    5219 1516.65
#Mann= 6 ,-1 , 0
  4763.8     .07       0  4961.7      .1       0  4972.1     .05       0
  4976.1      .1       0  5021.8     .07       0  5126.5    .035       0
Bank Sta=4972.1,4976.1
XS Rating Curve= 0 ,0
Exp/Cntr=0.3,0.1

Type RM Length L Ch R = 1 ,1126    ,164,164,164
BEGIN DESCRIPTION:
Mapping XS 8ec53660
END DESCRIPTION:
XS GIS Cut Line= 3
      1988365.07     13909438.83      1988182.58     13909534.19
      1988075.13      13909713.1
#Sta/Elev= 30
    4814 1512.37    4824 1509.41  4834.1 1507.18  4840.9 1506.32  4844.3 1506.43
  4854.4 1504.84    4868 1503.86  4871.4 1504.11    4916 1501.95  4921.1 1501.28
  4929.5 1501.33  4943.1 1500.21  4946.4 1500.33  4956.6 1499.81  4983.7 1496.83
  5008.8 1496.04    5009 1495.54  5012.5 1495.54  5012.8 1496.04  5090.9 1500.98
  5097.9 1500.83  5103.2 1501.46  5115.4 1501.73  5124.8 1502.81  5146.8  1503.3
  5153.8 1504.09  5173.2  1504.7  5184.8 1505.73  5202.8 1508.63  5228.6 1510.48
#Mann= 4 ,-1 , 0
    4814     .07       0  4946.4      .1       0  5008.8     .05       0
  5012.8      .1       0
Bank Sta=5008.8,5012.8
XS Rating Curve= 0 ,0
Exp/Cntr=0.3,0.1

Type RM Length L Ch R = 1 ,962     ,105,105,105
BEGIN DESCRIPTION:
Stream0072 2.0
END DESCRIPTION:
XS GIS Cut Line= 3
      1988375.04     13909374.99        1988075.       13909425.
        1987975.       13909725.
#Sta/Elev= 30
  4695.8 1512.48  4720.9 1510.78  4738.5 1508.13  4745.3 1506.16  4771.3  1503.7
  4809.7 1502.15  4864.5 1498.67  4879.7 1498.48  4919.2 1494.92  4934.4 1494.53
  4943.5 1493.51  4973.6 1494.02  4991.8 1493.09  4996.3 1492.45  4996.5 1491.95
    5000 1491.95  5000.3 1492.45  5002.1 1493.04  5012.6 1492.82  5043.2 1493.27
  5061.9 1495.15  5122.3  1498.1  5201.3 1503.25    5214  1504.2  5229.8 1506.41
  5247.7 1508.09  5270.9 1509.37    5293 1511.72  5305.7 1512.04  5316.2 1513.19
#Mann= 4 ,-1 , 0
  4695.8      .1       0  4996.3     .05       0  5000.3      .1       0
  5012.6    .035       0
Bank Sta=4996.3,5000.3
XS Rating Curve= 0 ,0
Exp/Cntr=0.3,0.1

Type RM Length L Ch R = 1 ,857     ,173,173,173
BEGIN DESCRIPTION:
Mapping XS 6be340dc
END DESCRIPTION:
XS GIS Cut Line= 3
      1988181.54     13909196.12      1987904.78     13909434.06
      1987880.92     13909530.16
#Sta/Elev= 30
  4761.8 1501.15  4860.5 1496.89  4864.5 1496.35  4888.2 1495.07  4896.1 1494.22
  4918.1 1490.76  4941.1 1488.39  4951.5 1487.54  4973.3  1486.7  4973.5  1486.2
    4977  1486.2  4977.3  1486.7  4987.1 1487.42  4991.7 1487.09  5018.8 1487.55
  5026.7 1488.48  5030.6 1488.48  5044.6 1490.43  5060.8 1491.84  5074.2 1494.28
  5078.1 1494.47  5082.1 1495.22    5116 1497.22  5147.9 1499.02  5153.5 1499.44
  5156.6 1500.11  5175.2 1501.25  5193.7 1501.38  5208.8 1500.32  5225.8 1500.93
#Mann= 4 ,-1 , 0
  4761.8      .1       0  4973.3     .05       0  4977.3      .1       0
    5116    .035       0
Bank Sta=4973.3,4977.3
XS Rating Curve= 0 ,0
Exp/Cntr=0.3,0.1

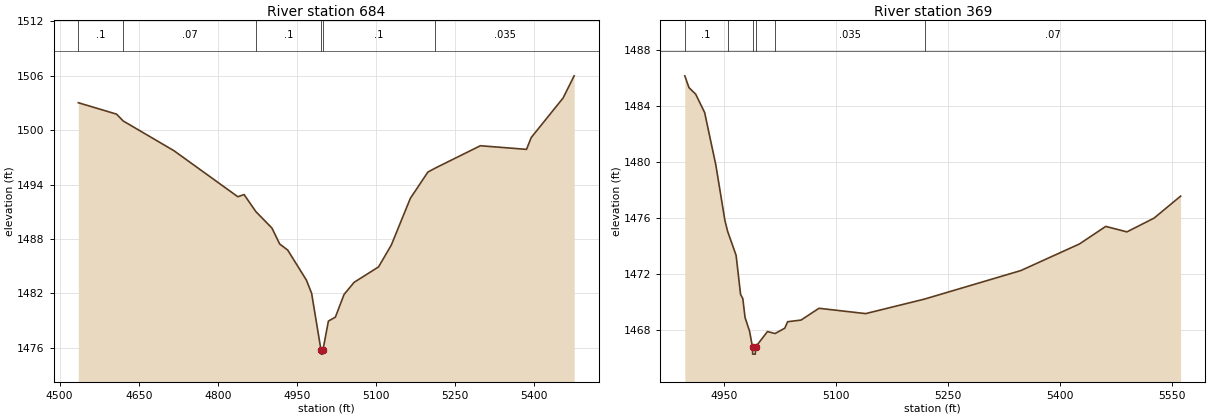
Type RM Length L Ch R = 1 ,684     ,315,315,315
BEGIN DESCRIPTION:
Stream0072 1.0
END DESCRIPTION:
XS GIS Cut Line= 4
      1988319.65     13909048.38      1988039.93     13909081.74
      1987839.61     13909280.19      1987798.85      13909654.9
#Sta/Elev= 30
  4535.5 1503.03    4608 1501.77  4620.5 1501.02  4716.7 1497.74  4838.1 1492.65
  4849.9 1492.89  4872.4    1491  4902.8 1489.19  4917.5 1487.43  4932.7 1486.76
  4968.2 1483.44  4978.1 1481.98  4995.7 1475.77    4996 1475.27  4999.5 1475.27
  4999.7 1475.77  5009.9 1478.92  5023.1 1479.35  5039.6 1481.86  5058.7  1483.2
    5105  1484.9  5129.2 1487.31  5165.4 1492.48  5198.6 1495.37  5212.9 1495.82
  5298.2 1498.28  5385.7 1497.88  5394.7 1499.19  5455.1 1503.55  5476.1    1506
#Mann= 6 ,-1 , 0
  4535.5      .1       0  4620.5     .07       0  4872.4      .1       0
  4995.7     .05       0  4999.7      .1       0  5212.9    .035       0
Bank Sta=4995.7,4999.7
XS Rating Curve= 0 ,0
Exp/Cntr=0.3,0.1

Type RM Length L Ch R = 1 ,369     ,0,0,0
BEGIN DESCRIPTION:
Stream0072 0.0
END DESCRIPTION:
XS GIS Cut Line= 4
      1987977.32     13908937.67      1987758.85     13908941.84
      1987653.97      13909123.4      1987624.26     13909357.34
#Sta/Elev= 30
  4897.8 1486.13  4903.4 1485.29  4912.4 1484.82  4924.4 1483.51  4939.4 1479.76
  4951.5 1475.82  4955.1 1475.05  4966.5 1473.33  4972.5 1470.54  4975.5 1470.24
  4978.5 1468.89  4984.5 1467.92  4988.5 1466.78  4988.7 1466.28  4992.2 1466.28
  4992.5 1466.78  5008.5 1467.89  5018.7 1467.75  5031.7 1468.13  5035.5 1468.59
  5053.5 1468.71  5077.5 1469.55    5140 1469.17  5219.1 1470.21  5347.8 1472.24
  5426.4 1474.14  5461.5 1475.39  5489.9    1475  5526.2 1475.98  5561.8 1477.55
#Mann= 6 ,-1 , 0
  4897.8      .1       0  4955.1      .1       0  4988.5     .05       0
  4992.5      .1       0  5018.7    .035       0  5219.1     .07       0
Bank Sta=4988.5,4992.5
XS Rating Curve= 0 ,0
Exp/Cntr=0.3,0.1

Chan Stop Cuts=-1
Use User Specified Reach Order=0
Composite Channel Slope=5