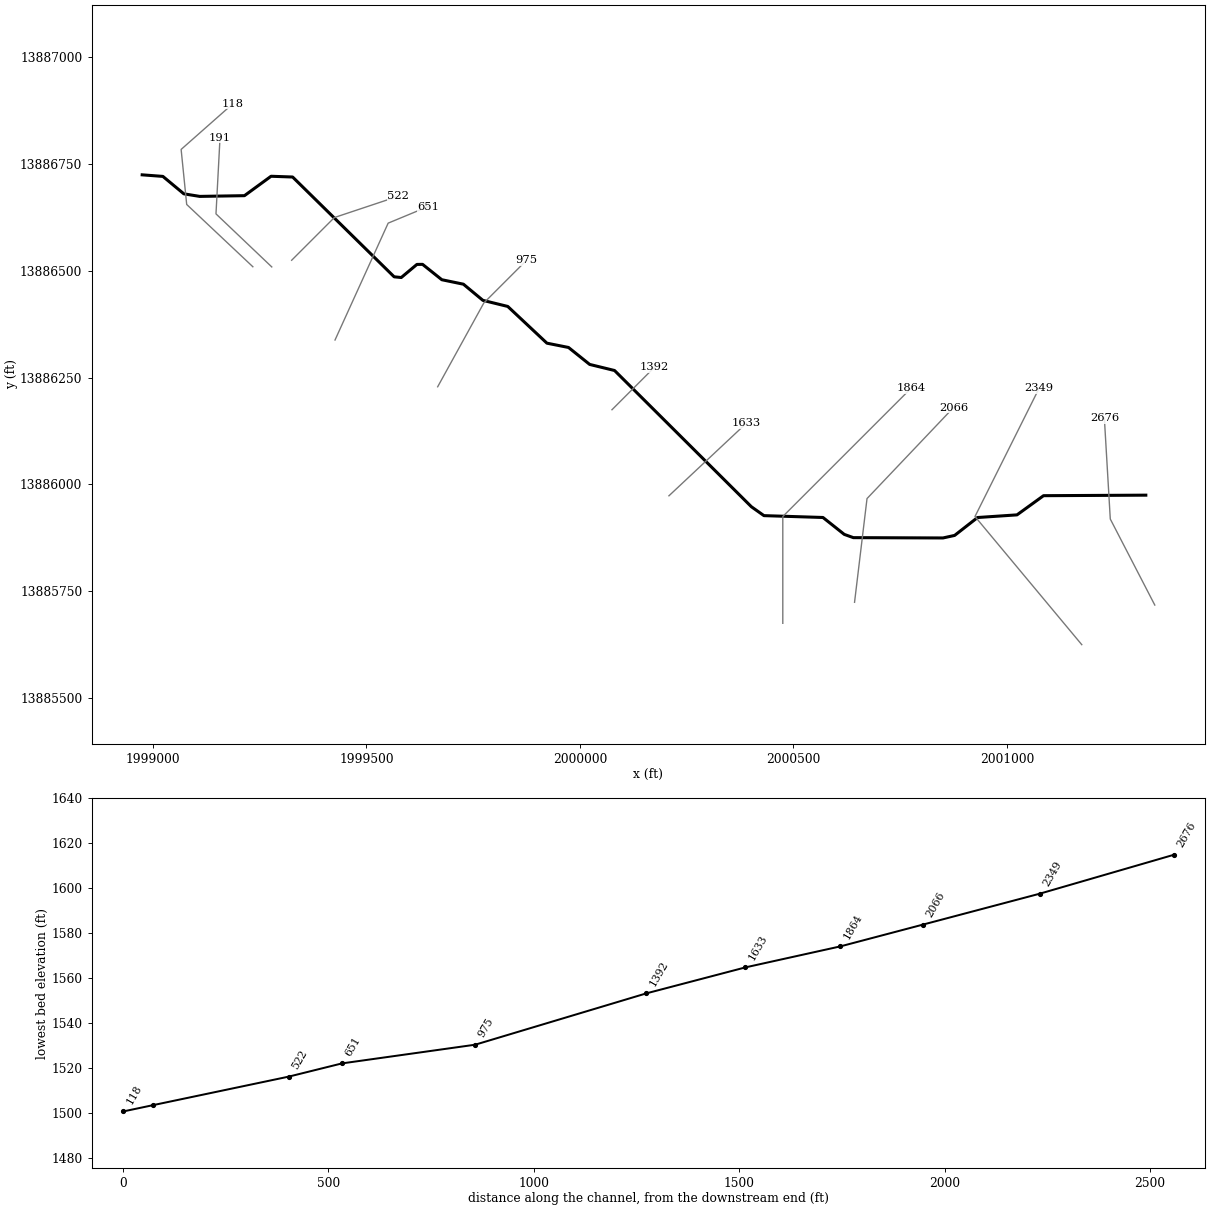
--- Stream0073.prj (project) ---

Proj Title=Stream0073 Base Level Engineering
Current Plan=p01
Default Exp/Contr=0.3,0.1
English Units
Geom File=g01
Flow File=f01
Plan File=p01
BEGIN DESCRIPTION:
Stream0073
END DESCRIPTION:

--- Stream0073.p01 (plan) ---

Plan Title=Multiple Run
Short Identifier=Multiple
Geom File=g01
Flow File=f01
Subcritical Flow
K Sum by GR= 0
Std Step Tol= 0.01
Critical Tol= 0.01
Num of Std Step Trials= 20
Max Error Tol= 0.3
Flow Tol Ratio= 0.001
Split Flow NTrial= 30
Split Flow Tol= 0.02
Split Flow Ratio= 0.02
Log Output Level= 0
Friction Slope Method= 1
Unsteady Friction Slope Method= 2
Unsteady Bridges Friction Slope Method= 1
Parabolic Critical Depth
Global Vel Dist=  1 , 1 , 1
Global Log Level= 0
CheckData=True
Encroach Param= -1, 0, 0, 0
BEGIN DESCRIPTION:
Multiple Run
END DESCRIPTION:

--- Stream0073.f01 (steady flow) ---

Flow Title=Multiple
Number of Profiles=7
Profile Names=10-year,25-year,50-year,1pct_min,100-year,1pct_plu,500-year
River Rch & RM= Stream0073,Reach-1,2676
     141     209     266     166     332     662     504
River Rch & RM= Stream0073,Reach-1,2349
     373     597     800     523    1044    2083    1750
Boundary for River Rch & Prof#=Stream0073,Reach-1,1
Up Type=0
Dn Type=3
Dn Slope=0.005
Boundary for River Rch & Prof#=Stream0073,Reach-1,2
Up Type=0
Dn Type=3
Dn Slope=0.005
Boundary for River Rch & Prof#=Stream0073,Reach-1,3
Up Type=0
Dn Type=3
Dn Slope=0.005
Boundary for River Rch & Prof#=Stream0073,Reach-1,4
Up Type=0
Dn Type=3
Dn Slope=0.005
Boundary for River Rch & Prof#=Stream0073,Reach-1,5
Up Type=0
Dn Type=3
Dn Slope=0.005
Boundary for River Rch & Prof#=Stream0073,Reach-1,6
Up Type=0
Dn Type=3
Dn Slope=0.005
Boundary for River Rch & Prof#=Stream0073,Reach-1,7
Up Type=0
Dn Type=3
Dn Slope=0.005

--- Stream0073.g01 (geometry) ---

Geom Title=Existing Conditions

River Reach=Stream0073,Reach-1
Reach XY= 30
      2001325.00     13885975.00      2001085.50     13885973.78
      2001023.40     13885928.86      2000930.98     13885922.64
      2000877.34     13885880.74      2000850.08     13885874.80
      2000640.22     13885875.52      2000618.94     13885883.14
      2000569.06     13885922.73      2000430.86     13885927.07
      2000401.47     13885947.86      2000081.06     13886266.86
      2000022.81     13886281.10      1999973.27     13886320.81
      1999922.71     13886330.85      1999831.05     13886416.84
      1999772.81     13886431.11      1999727.19     13886468.95
      1999676.63     13886479.41      1999631.55     13886515.41
      1999618.27     13886515.23      1999581.66     13886484.60
      1999565.00     13886486.24      1999327.30     13886719.91
      1999276.75     13886721.66      1999214.50     13886676.23
      1999109.83     13886674.52      1999072.58     13886680.53
      1999023.49     13886721.35      1998975.00     13886725.00

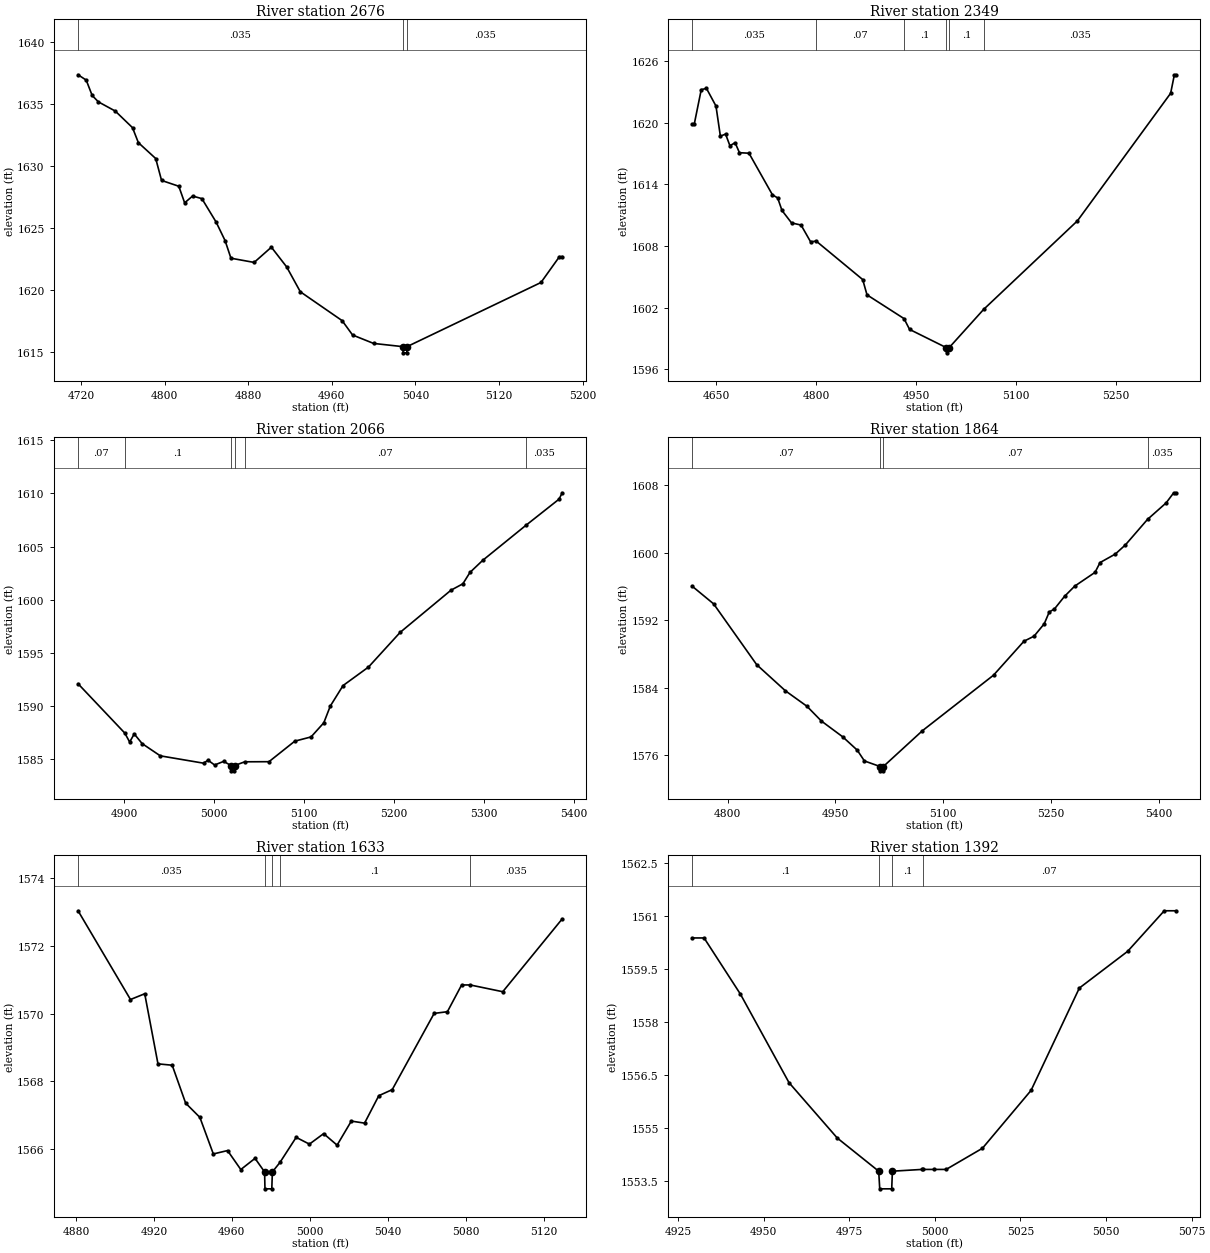
Type RM Length L Ch R = 1,2676,327,327,327
BEGIN DESCRIPTION:
Stream0073 6.0
END DESCRIPTION:
XS GIS Cut Line= 3
      2001346.00     13885717.68      2001241.82     13885919.09
      2001227.93     13886155.22
#Sta/Elev= 30
  4717.2 1637.39  4725.0 1636.96  4730.7 1635.72  4736.7 1635.20  4752.8 1634.46
  4769.3 1633.12  4774.9 1631.91  4791.5 1630.63  4797.1 1628.86  4813.6 1628.39
  4819.2 1627.05  4826.8 1627.60  4835.7 1627.39  4849.3 1625.50  4857.9 1624.00
  4863.5 1622.58  4885.7 1622.24  4902.2 1623.47  4916.8 1621.88  4929.9 1619.87
  4969.9 1617.54  4979.9 1616.38  5000.0 1615.70  5028.0 1615.44  5028.3 1614.94
  5031.8 1614.94  5032.0 1615.44  5160.2 1620.62  5177.9 1622.71  5180.5 1622.71
#Mann=3,-1,0
  4717.2   0.035       0  5028.0   0.035       0  5032.0   0.035       0
Bank Sta=5028,5032
Exp/Cntr=0.3,0.1

Type RM Length L Ch R = 1,2349,283,283,283
BEGIN DESCRIPTION:
Stream0073 5.0
END DESCRIPTION:
XS GIS Cut Line= 3
      2001175.03     13885624.96      2000925.00     13885925.00
      2001075.01     13886225.03
#Sta/Elev= 30
  4613.9 1619.87  4617.2 1619.87  4627.6 1623.20  4635.4 1623.33  4649.7 1621.61
  4656.3 1618.68  4664.1 1618.88  4670.6 1617.75  4678.4 1618.04  4684.9 1617.07
  4699.2 1617.02  4734.4 1612.97  4742.2 1612.67  4748.7 1611.45  4763.0 1610.24
  4777.3 1610.03  4791.6 1608.40  4800.0 1608.47  4869.7 1604.73  4876.2 1603.24
  4931.7 1600.93  4940.0 1599.88  4995.3 1598.10  4995.5 1597.60  4999.3 1598.10
  5051.0 1601.82  5191.7 1610.44  5331.5 1622.85  5337.1 1624.65  5339.9 1624.65
#Mann=6,-1,0
  4613.9   0.035       0  4800.0    0.07       0  4931.7     0.1       0
  4995.3    0.05       0  4999.3     0.1       0  5051.0   0.035       0
Bank Sta=4995.3,4999.3
Exp/Cntr=0.3,0.1

Type RM Length L Ch R = 1,2066,202,202,202
BEGIN DESCRIPTION:
Mapping XS a753b141
END DESCRIPTION:
XS GIS Cut Line= 3
      2000643.00     13885724.17      2000672.20     13885967.01
      2000874.73     13886180.14
#Sta/Elev= 30
  4848.5 1592.10  4900.5 1587.46  4905.9 1586.62  4911.0 1587.38  4919.8 1586.47
  4940.0 1585.32  4988.1 1584.63  4993.1 1584.91  5000.4 1584.46  5010.5 1584.80
  5018.6 1584.41  5018.8 1583.91  5022.3 1583.91  5022.6 1584.41  5034.0 1584.76
  5060.9 1584.77  5089.6 1586.70  5107.7 1587.10  5121.9 1588.43  5129.1 1590.00
  5143.3 1591.93  5171.6 1593.67  5206.8 1596.93  5263.4 1600.90  5276.6 1601.50
  5284.5 1602.57  5298.6 1603.70  5346.6 1606.99  5383.6 1609.46  5387.1 1610.06
#Mann=6,-1,0
  4848.5    0.07       0  4900.5     0.1       0  5018.6    0.05       0
  5022.6     0.1       0  5034.0    0.07       0  5346.6   0.035       0
Bank Sta=5018.6,5022.6
Exp/Cntr=0.3,0.1

Type RM Length L Ch R = 1,1864,231,231,231
BEGIN DESCRIPTION:
Stream0073 4.0
END DESCRIPTION:
XS GIS Cut Line= 3
      2000475.00     13885674.95      2000475.00     13885925.00
      2000774.99     13886224.99
#Sta/Elev= 30
  4750.3 1596.03  4780.3 1593.93  4840.3 1586.73  4880.3 1583.64  4910.3 1581.81
  4930.3 1580.07  4960.3 1578.18  4980.3 1576.62  4990.3 1575.34  5012.5 1574.67
  5012.7 1574.17  5016.2 1574.17  5016.5 1574.67  5071.1 1578.92  5170.1 1585.49
  5212.5 1589.51  5226.6 1590.11  5240.8 1591.58  5247.8 1592.98  5254.9 1593.32
  5269.0 1594.82  5283.2 1596.03  5311.5 1597.66  5318.5 1598.82  5339.8 1599.83
  5353.9 1600.92  5384.6 1603.93  5410.5 1605.88  5421.1 1607.08  5424.6 1607.08
#Mann=4,-1,0
  4750.3    0.07       0  5012.5    0.05       0  5016.5    0.07       0
  5384.6   0.035       0
Bank Sta=5012.5,5016.5
Exp/Cntr=0.3,0.1

Type RM Length L Ch R = 1,1633,241,241,241
BEGIN DESCRIPTION:
Mapping XS 9cd47610
END DESCRIPTION:
XS GIS Cut Line= 2
      2000208.40     13885973.50      2000389.63     13886143.37
#Sta/Elev= 30
  4881.1 1573.04  4908.0 1570.42  4915.3 1570.59  4922.1 1568.52  4929.4 1568.48
  4936.3 1567.36  4943.6 1566.94  4950.5 1565.86  4957.8 1565.96  4964.6 1565.40
  4971.9 1565.73  4976.8 1565.33  4977.0 1564.83  4980.5 1564.83  4980.8 1565.33
  4984.7 1565.61  4993.0 1566.35  4999.8 1566.15  5007.1 1566.46  5014.0 1566.12
  5021.3 1566.83  5028.1 1566.77  5035.4 1567.58  5042.3 1567.76  5063.8 1570.01
  5070.6 1570.06  5077.9 1570.85  5082.3 1570.85  5099.0 1570.65  5129.5 1572.80
#Mann=5,-1,0
  4881.1   0.035       0  4976.8    0.05       0  4980.8   0.035       0
  4984.7     0.1       0  5082.3   0.035       0
Bank Sta=4976.8,4980.8
Exp/Cntr=0.3,0.1

Type RM Length L Ch R = 1,1392,417,417,417
BEGIN DESCRIPTION:
Stream0073 3.0
END DESCRIPTION:
XS GIS Cut Line= 3
      2000075.02     13886175.02      2000125.00     13886225.00
      2000175.01     13886275.01
#Sta/Elev= 19
  4929.1 1560.39  4932.6 1560.39  4943.2 1558.80  4957.4 1556.29  4971.5 1554.72
  4983.6 1553.78  4983.9 1553.28  4987.4 1553.28  4987.6 1553.78  4996.2 1553.83
  4996.4 1553.83  4999.8 1553.83  5003.3 1553.83  5013.9 1554.43  5028.1 1556.07
  5042.2 1558.97  5056.3 1560.01  5067.0 1561.16  5070.5 1561.16
#Mann=4,-1,0
  4929.1     0.1       0  4983.6    0.05       0  4987.6     0.1       0
  4996.4    0.07       0
Bank Sta=4983.6,4987.6
Exp/Cntr=0.3,0.1

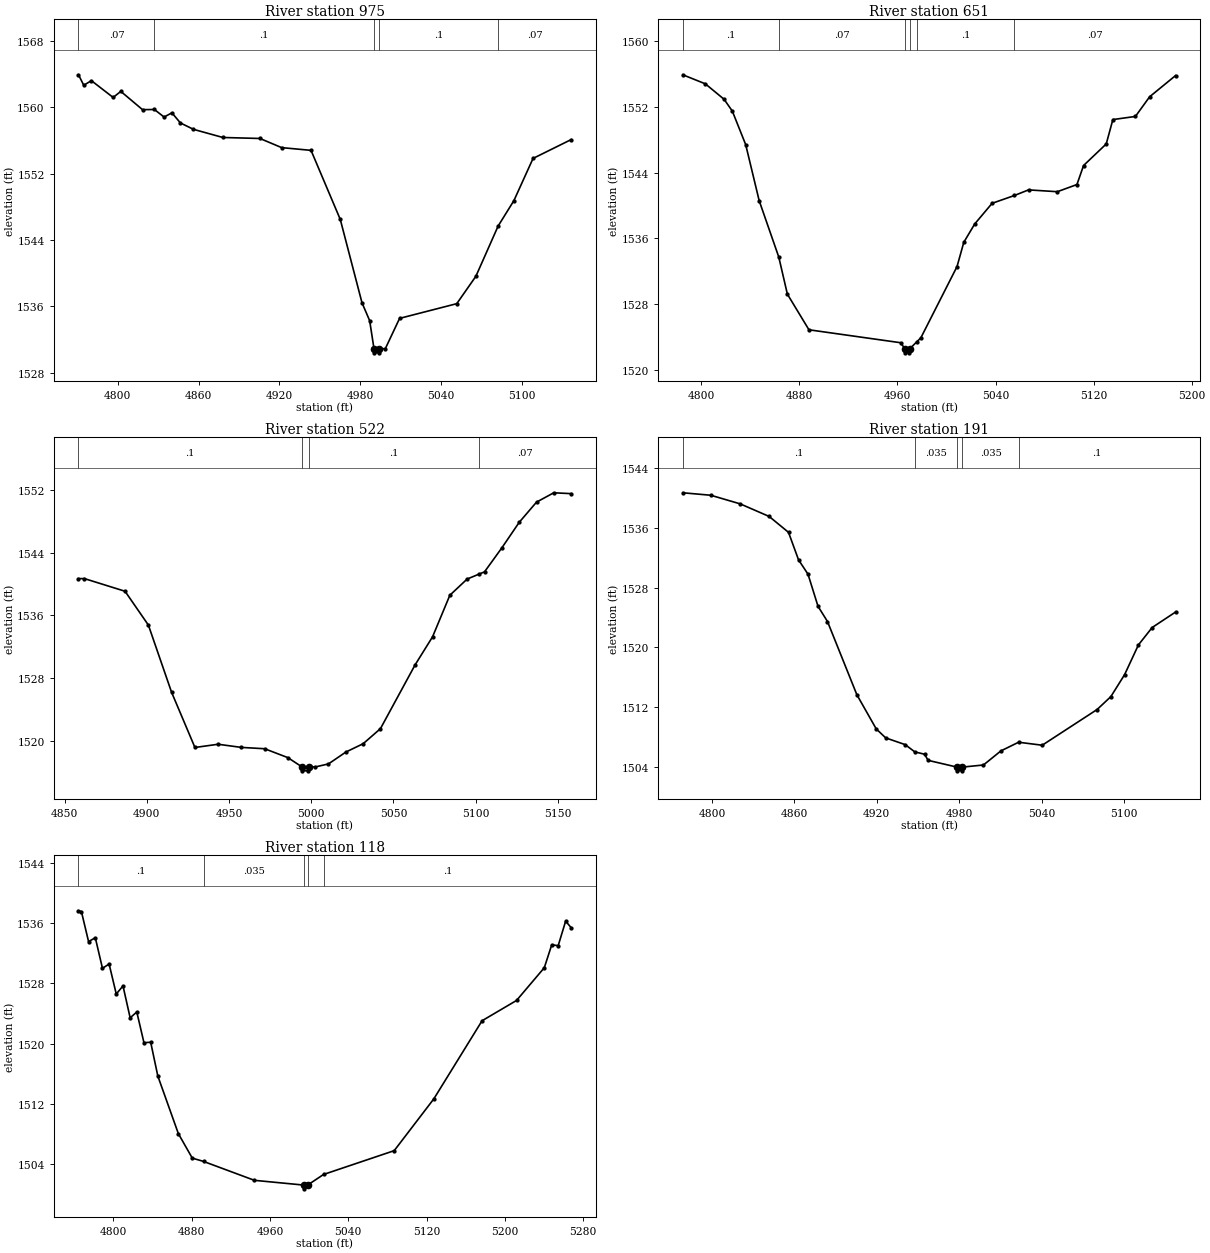
Type RM Length L Ch R = 1,975,324,324,324
BEGIN DESCRIPTION:
Stream0073 2.0
END DESCRIPTION:
XS GIS Cut Line= 3
      1999666.91     13886228.75      1999775.00     13886425.00
      1999875.02     13886525.02
#Sta/Elev= 30
  4770.9 1563.90  4774.8 1562.64  4780.5 1563.19  4796.6 1561.17  4802.3 1561.90
  4818.4 1559.70  4827.2 1559.72  4834.4 1558.81  4840.2 1559.32  4846.5 1558.10
  4856.2 1557.33  4878.0 1556.35  4905.5 1556.23  4921.6 1555.13  4943.4 1554.80
  4965.1 1546.48  4981.2 1536.45  4986.9 1534.29  4990.1 1530.92  4990.3 1530.42
  4993.8 1530.42  4994.1 1530.92  4998.5 1530.92  5009.1 1534.57  5051.5 1536.34
  5065.7 1539.64  5082.2 1545.69  5093.9 1548.75  5108.1 1553.83  5136.4 1556.10
#Mann=5,-1,0
  4770.9    0.07       0  4827.2     0.1       0  4990.1    0.05       0
  4994.1     0.1       0  5082.2    0.07       0
Bank Sta=4990.1,4994.1
Exp/Cntr=0.3,0.1

Type RM Length L Ch R = 1,651,129,129,129
BEGIN DESCRIPTION:
Mapping XS 181e16b4
END DESCRIPTION:
XS GIS Cut Line= 3
      1999426.55     13886338.25      1999550.97     13886611.91
      1999644.54     13886650.70
#Sta/Elev= 30
  4784.9 1555.88  4803.3 1554.78  4818.6 1552.90  4825.3 1551.47  4836.2 1547.40
  4847.2 1540.59  4863.2 1533.74  4870.2 1529.24  4887.8 1524.91  4962.5 1523.34
  4966.1 1522.61  4966.3 1522.11  4969.8 1522.11  4970.1 1522.61  4975.9 1523.47
  4979.1 1523.94  5008.6 1532.59  5014.1 1535.53  5023.0 1537.76  5037.2 1540.27
  5055.4 1541.22  5066.9 1541.90  5090.4 1541.68  5106.4 1542.55  5111.8 1544.86
  5130.3 1547.48  5135.7 1550.44  5154.1 1550.82  5165.7 1553.21  5186.8 1555.78
#Mann=6,-1,0
  4784.9     0.1       0  4863.2    0.07       0  4966.1    0.05       0
  4970.1    0.07       0  4975.9     0.1       0  5055.4    0.07       0
Bank Sta=4966.1,4970.1
Exp/Cntr=0.3,0.1

Type RM Length L Ch R = 1,522,331,331,331
BEGIN DESCRIPTION:
Stream0073 1.0
END DESCRIPTION:
XS GIS Cut Line= 3
      1999324.97     13886524.97      1999425.00     13886625.00
      1999575.02     13886675.01
#Sta/Elev= 30
  4858.5 1540.69  4862.1 1540.69  4886.8 1539.08  4901.0 1534.78  4915.1 1526.24
  4929.3 1519.22  4943.4 1519.63  4957.5 1519.23  4971.7 1519.06  4985.8 1517.93
  4994.4 1516.75  4994.7 1516.25  4998.2 1516.25  4998.4 1516.75  5002.6 1516.75
  5010.5 1517.13  5021.1 1518.64  5031.6 1519.70  5042.1 1521.61  5063.2 1529.73
  5073.8 1533.29  5084.3 1538.57  5094.8 1540.63  5102.3 1541.28  5105.4 1541.55
  5115.9 1544.59  5126.5 1547.85  5137.0 1550.41  5147.5 1551.60  5158.1 1551.49
#Mann=4,-1,0
  4858.5     0.1       0  4994.4    0.05       0  4998.4     0.1       0
  5102.3    0.07       0
Bank Sta=4994.4,4998.4
Exp/Cntr=0.3,0.1

Type RM Length L Ch R = 1,191,73,73,73
BEGIN DESCRIPTION:
Stream0073 0.0
END DESCRIPTION:
XS GIS Cut Line= 3
      1999278.43     13886509.38      1999147.83     13886633.60
      1999157.29     13886812.01
#Sta/Elev= 30
  4778.7 1540.66  4799.1 1540.33  4820.5 1539.18  4841.6 1537.50  4855.7 1535.38
  4863.0 1531.71  4869.9 1529.79  4877.2 1525.50  4884.1 1523.47  4905.5 1513.69
  4919.6 1509.13  4926.5 1507.93  4940.7 1507.03  4947.7 1506.06  4954.8 1505.75
  4957.4 1504.93  4978.4 1504.03  4978.6 1503.53  4982.1 1503.53  4982.4 1504.03
  4997.7 1504.31  5010.4 1506.19  5023.3 1507.35  5040.5 1506.95  5080.5 1511.72
  5090.5 1513.44  5100.5 1516.37  5110.6 1520.35  5120.6 1522.67  5137.6 1524.73
#Mann=5,-1,0
  4778.7     0.1       0  4947.7   0.035       0  4978.4   0.035       0
  4982.4   0.035       0  5023.3     0.1       0
Bank Sta=4978.4,4982.4
Exp/Cntr=0.3,0.1

Type RM Length L Ch R = 1,118,0,0,0
BEGIN DESCRIPTION:
Stream0073 0.1
END DESCRIPTION:
XS GIS Cut Line= 4
      1999234.16     13886509.80      1999079.24     13886655.62
      1999066.22     13886784.52      1999187.12     13886891.28
#Sta/Elev= 30
  4764.3 1537.63  4767.3 1537.52  4774.6 1533.54  4781.5 1534.05  4788.8 1529.99
  4795.6 1530.56  4802.9 1526.58  4809.8 1527.65  4817.1 1523.42  4823.9 1524.19
  4831.2 1520.12  4838.1 1520.17  4845.4 1515.68  4866.4 1508.03  4880.6 1504.79
  4892.1 1504.35  4944.1 1501.84  4994.5 1501.21  4994.8 1500.71  4998.5 1501.21
  5014.8 1502.62  5087.0 1505.78  5127.5 1512.66  5176.8 1523.03  5212.0 1525.72
  5240.4 1530.07  5248.0 1533.11  5254.6 1533.00  5262.2 1536.25  5267.9 1535.38
#Mann=5,-1,0
  4764.3     0.1       0  4892.1   0.035       0  4994.5   0.035       0
  4998.5   0.035       0  5014.8     0.1       0
Bank Sta=4994.5,4998.5
Exp/Cntr=0.3,0.1

Chan Stop Cuts=-1