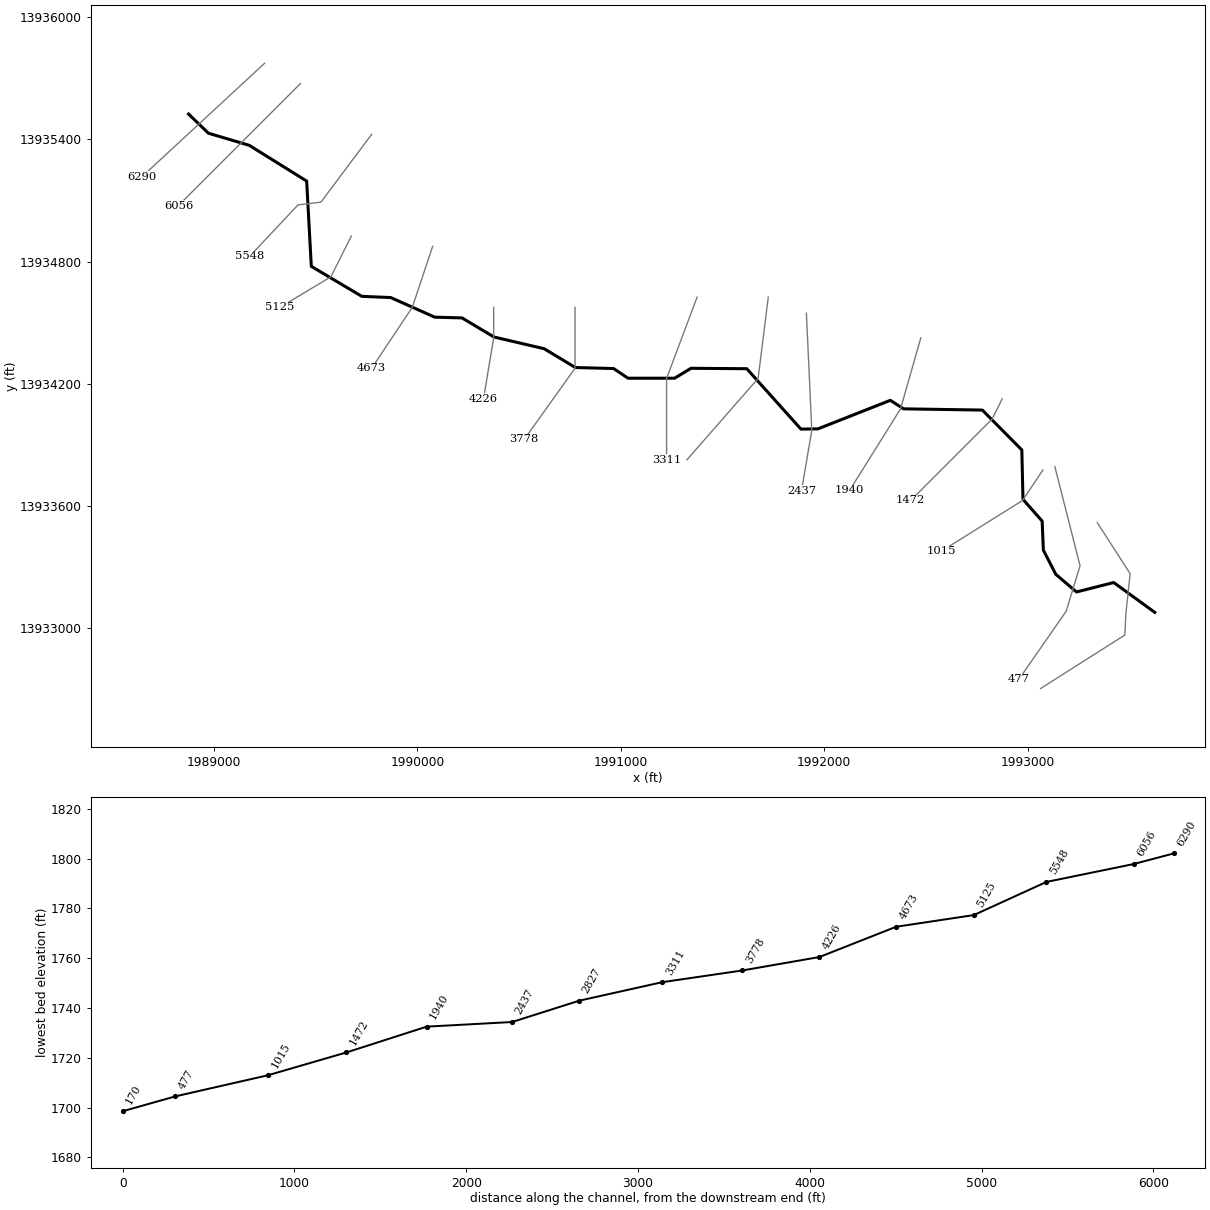
--- Stream0074.prj (project) ---

Proj Title=Stream0074 Base Level Engineering
Current Plan=p01
Default Exp/Contr=0.3,0.1
English Units
Geom File=g01
Flow File=f01
Plan File=p01
Y Axis Title=Elevation
X Axis Title(PF)=Main Channel Distance
X Axis Title(XS)=Station
BEGIN DESCRIPTION:
Stream0074
END DESCRIPTION:
DSS Export Rating Curves= 0
DSS Export Rating Curve Sorted= 0
DSS Export Volume Flow Curves= 0
DXF OffsetX= 0
DXF OffsetY= 0
DXF ScaleX= 1
DXF ScaleY= 10

--- Stream0074.p01 (plan) ---

Plan Title=Multiple Run
Short Identifier=Multiple
Geom File=g01
Flow File=f01
Subcritical Flow
K Sum by GR= 0
Std Step Tol= 0.01
Critical Tol= 0.01
Num of Std Step Trials= 20
Max Error Tol= 0.3
Flow Tol Ratio= 0.001
Split Flow NTrial= 30
Split Flow Tol= 0.02
Split Flow Ratio= 0.02
Log Output Level= 0
Friction Slope Method= 1
Unsteady Friction Slope Method= 2
Unsteady Bridges Friction Slope Method= 1
Parabolic Critical Depth
Global Vel Dist=  1 , 1 , 1
Global Log Level= 0
CheckData=True
Encroach Param= -1, 0, 0, 0
BEGIN DESCRIPTION:
Multiple Run
END DESCRIPTION:

--- Stream0074.f01 (steady flow) ---

Flow Title=Multiple
Program Version=4.10
Number of Profiles= 7
Profile Names=10-year,25-year,50-year,1pct_min,100-year,1pct_plu,500-year
River Rch & RM=Stream0074,Reach-1         ,6290
    1057    1822    2563    1750    3491    6966    6425
River Rch & RM=Stream0074,Reach-1         ,3778
    1178    2039    2875    1966    3922    7825    7243
Boundary for River Rch & Prof#=Stream0074,Reach-1         , 1
Up Type= 0
Dn Type= 3
Dn Slope=0.008
Boundary for River Rch & Prof#=Stream0074,Reach-1         , 2
Up Type= 0
Dn Type= 3
Dn Slope=0.008
Boundary for River Rch & Prof#=Stream0074,Reach-1         , 3
Up Type= 0
Dn Type= 3
Dn Slope=0.008
Boundary for River Rch & Prof#=Stream0074,Reach-1         , 4
Up Type= 0
Dn Type= 3
Dn Slope=0.008
Boundary for River Rch & Prof#=Stream0074,Reach-1         , 5
Up Type= 0
Dn Type= 3
Dn Slope=0.008
Boundary for River Rch & Prof#=Stream0074,Reach-1         , 6
Up Type= 0
Dn Type= 3
Dn Slope=0.008
Boundary for River Rch & Prof#=Stream0074,Reach-1         , 7
Up Type= 0
Dn Type= 3
Dn Slope=0.008
DSS Import GetInterval= 0
DSS Import GetPeak= 0
DSS Import FillOption= 0

--- Stream0074.g01 (geometry) ---

Geom Title=Existing Conditions

River Reach=Stream0074,Reach-1
Reach XY= 30
      1988875.00     13935525.00      1988972.68     13935430.79
      1989173.42     13935371.17      1989455.56     13935195.55
      1989478.45     13934776.25      1989726.56     13934628.76
      1989869.06     13934622.73      1990085.51     13934526.23
      1990219.07     13934522.75      1990376.58     13934428.83
      1990623.42     13934371.17      1990776.55     13934278.75
      1990964.49     13934273.78      1991035.50     13934226.22
      1991264.50     13934226.22      1991345.03     13934274.93
      1991619.16     13934272.95      1991885.48     13933975.93
      1991969.02     13933977.16      1992325.00     13934117.44
      1992390.16     13934075.66      1992777.45     13934069.54
      1992971.46     13933873.54      1992977.07     13933630.86
      1993071.44     13933523.53      1993077.25     13933380.93
      1993138.61     13933261.76      1993240.21     13933175.24
      1993423.28     13933221.66      1993625.00     13933075.00

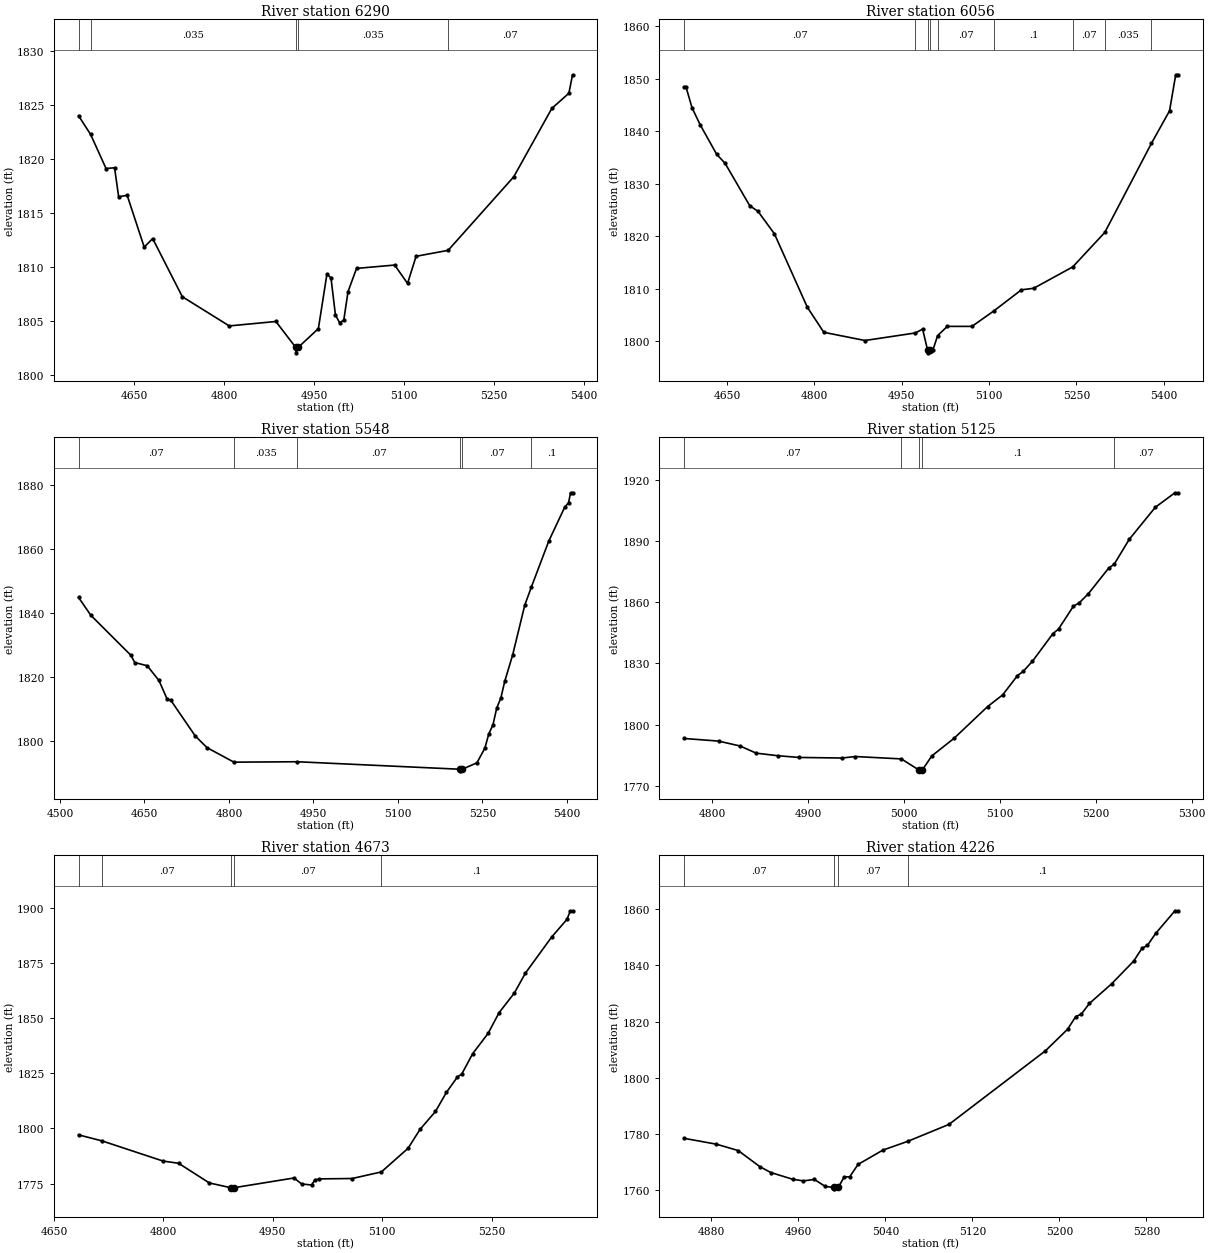
Type RM Length L Ch R = 1,6290,234,234,234
BEGIN DESCRIPTION:
Stream0074 13.0
END DESCRIPTION:
XS GIS Cut Line= 2
      1989249.33     13935775.13      1988645.18     13935216.12
#Sta/Elev= 30
  4557.8 1824.01  4577.9 1822.28  4603.6 1819.13  4617.8 1819.20  4624.6 1816.52
  4638.8 1816.65  4667.2 1811.86  4681.3 1812.65  4730.7 1807.27  4808.9 1804.57
  4886.6 1804.98  4919.7 1802.58  4920.0 1802.08  4923.7 1802.58  4957.4 1804.32
  4971.6 1809.35  4978.4 1809.02  4985.8 1805.59  4992.6 1804.88  4999.7 1805.09
  5006.8 1807.74  5021.0 1809.89  5084.5 1810.20  5106.0 1808.50  5120.2 1811.01
  5173.6 1811.56  5282.9 1818.36  5346.4 1824.69  5374.8 1826.09  5380.9 1827.80
#Mann=5,-1,0
  4557.8    0.07       0  4577.9   0.035       0  4919.7   0.035       0
  4923.7   0.035       0  5173.6    0.07       0
Bank Sta=4919.7,4923.7
Exp/Cntr=0.3,0.1

Type RM Length L Ch R = 1,6056,508,508,508
BEGIN DESCRIPTION:
Stream0074 12.0
END DESCRIPTION:
XS GIS Cut Line= 3
      1989425.03     13935675.03      1989125.00     13935375.00
      1988824.97     13935074.97
#Sta/Elev= 30
  4575.7 1848.50  4579.3 1848.50  4589.9 1844.47  4604.0 1841.21  4632.3 1835.60
  4646.4 1833.95  4688.9 1825.84  4703.0 1824.78  4731.3 1820.49  4787.9 1806.49
  4816.2 1801.72  4886.9 1800.16  4973.6 1801.60  4985.9 1802.33  4994.5 1798.31
  4994.7 1797.81  4998.5 1798.31  5003.5 1798.31  5011.7 1801.09  5028.3 1802.85
  5070.7 1802.85  5108.7 1805.83  5155.6 1809.81  5176.8 1810.11  5243.9 1814.19
  5298.9 1820.75  5379.1 1837.74  5410.1 1843.91  5420.7 1850.78  5424.3 1850.78
#Mann=9,-1,0
  4575.7    0.07       0  4973.6     0.1       0  4994.5    0.05       0
  4998.5     0.1       0  5011.7    0.07       0  5108.7     0.1       0
  5243.9    0.07       0  5298.9   0.035       0  5379.1    0.07       0
Bank Sta=4994.5,4998.5
Exp/Cntr=0.3,0.1

Type RM Length L Ch R = 1,5548,423,423,423
BEGIN DESCRIPTION:
Stream0074 11.0
END DESCRIPTION:
XS GIS Cut Line= 4
      1989775.00     13935424.99      1989525.63     13935091.81
      1989412.99     13935078.28      1989174.97     13934824.97
#Sta/Elev= 30
  4533.0 1844.74  4554.9 1839.16  4625.7 1826.74  4632.9 1824.42  4654.9 1823.43
  4675.7 1818.84  4690.3 1813.03  4696.6 1812.71  4740.3 1801.48  4761.2 1797.85
  4808.9 1793.33  4921.5 1793.46  5210.1 1791.12  5210.4 1790.62  5214.1 1791.12
  5240.4 1793.11  5254.6 1797.74  5261.5 1802.17  5268.8 1804.91  5275.6 1810.22
  5282.9 1813.34  5289.8 1818.57  5303.9 1826.82  5325.4 1842.37  5337.0 1847.95
  5367.9 1862.30  5396.2 1872.89  5403.1 1874.31  5406.7 1877.42  5410.2 1877.42
#Mann=6,-1,0
  4533.0    0.07       0  4808.9   0.035       0  4921.5    0.07       0
  5210.1    0.05       0  5214.1    0.07       0  5337.0     0.1       0
Bank Sta=5210.1,5214.1
Exp/Cntr=0.3,0.1

Type RM Length L Ch R = 1,5125,452,452,452
BEGIN DESCRIPTION:
Stream0074 10.0
END DESCRIPTION:
XS GIS Cut Line= 3
      1989675.00     13934925.01      1989575.00     13934725.00
      1989324.97     13934574.98
#Sta/Elev= 30
  4770.4 1793.19  4806.7 1791.89  4829.1 1789.48  4845.9 1785.97  4868.2 1784.73
  4890.6 1783.87  4935.3 1783.59  4949.3 1784.32  4997.3 1783.15  5015.3 1777.80
  5015.6 1777.30  5019.3 1777.80  5029.0 1784.61  5052.3 1793.28  5087.3 1808.86
  5102.9 1814.54  5118.4 1824.02  5124.2 1826.04  5134.0 1831.06  5155.3 1844.58
  5161.2 1846.88  5176.7 1858.05  5182.6 1859.64  5192.3 1864.19  5213.6 1876.82
  5219.2 1878.62  5235.0 1890.92  5262.2 1906.62  5282.6 1913.72  5285.6 1913.72
#Mann=5,-1,0
  4770.4    0.07       0  4997.3     0.1       0  5015.3    0.05       0
  5019.3     0.1       0  5219.2    0.07       0
Bank Sta=5015.3,5019.3
Exp/Cntr=0.3,0.1

Type RM Length L Ch R = 1,4673,447,447,447
BEGIN DESCRIPTION:
Stream0074 9.0
END DESCRIPTION:
XS GIS Cut Line= 3
      1990074.99     13934874.97      1989975.00     13934575.00
      1989774.98     13934274.96
#Sta/Elev= 30
  4683.8 1797.08  4716.0 1794.34  4799.7 1785.19  4820.8 1784.21  4863.0 1775.27
  4892.6 1773.11  4892.8 1772.61  4896.6 1773.11  4978.9 1777.53  4989.5 1774.82
  5003.0 1774.35  5007.5 1776.60  5013.5 1777.12  5058.6 1777.29  5098.7 1780.28
  5135.2 1790.97  5151.7 1799.58  5172.8 1807.69  5187.8 1816.33  5202.8 1823.31
  5208.8 1824.65  5223.8 1833.90  5244.9 1843.09  5259.9 1852.45  5280.9 1861.40
  5296.0 1870.40  5332.0 1886.78  5353.0 1894.80  5357.6 1898.68  5360.6 1898.68
#Mann=5,-1,0
  4683.8   0.035       0  4716.0    0.07       0  4892.6    0.05       0
  4896.6    0.07       0  5098.7     0.1       0
Bank Sta=4892.6,4896.6
Exp/Cntr=0.3,0.1

Type RM Length L Ch R = 1,4226,448,448,448
BEGIN DESCRIPTION:
Stream0074 8.0
END DESCRIPTION:
XS GIS Cut Line= 3
      1990375.00     13934575.01      1990375.00     13934425.00
      1990324.99     13934124.95
#Sta/Elev= 30
  4854.6 1778.45  4884.6 1776.34  4904.6 1774.08  4924.6 1768.32  4934.6 1766.26
  4954.6 1763.87  4964.6 1763.28  4974.6 1763.80  4984.6 1761.32  4992.6 1760.95
  4992.9 1760.45  4996.6 1760.95  5002.1 1764.72  5007.1 1764.72  5014.8 1769.14
  5037.6 1774.23  5060.5 1777.36  5098.4 1783.39  5187.1 1809.59  5207.4 1817.24
  5215.0 1821.79  5220.0 1822.61  5227.6 1826.47  5247.9 1833.42  5268.2 1841.50
  5275.8 1846.03  5280.9 1847.14  5288.5 1851.40  5306.2 1859.43  5308.8 1859.43
#Mann=4,-1,0
  4854.6    0.07       0  4992.6    0.05       0  4996.6    0.07       0
  5060.5     0.1       0
Bank Sta=4992.6,4996.6
Exp/Cntr=0.3,0.1

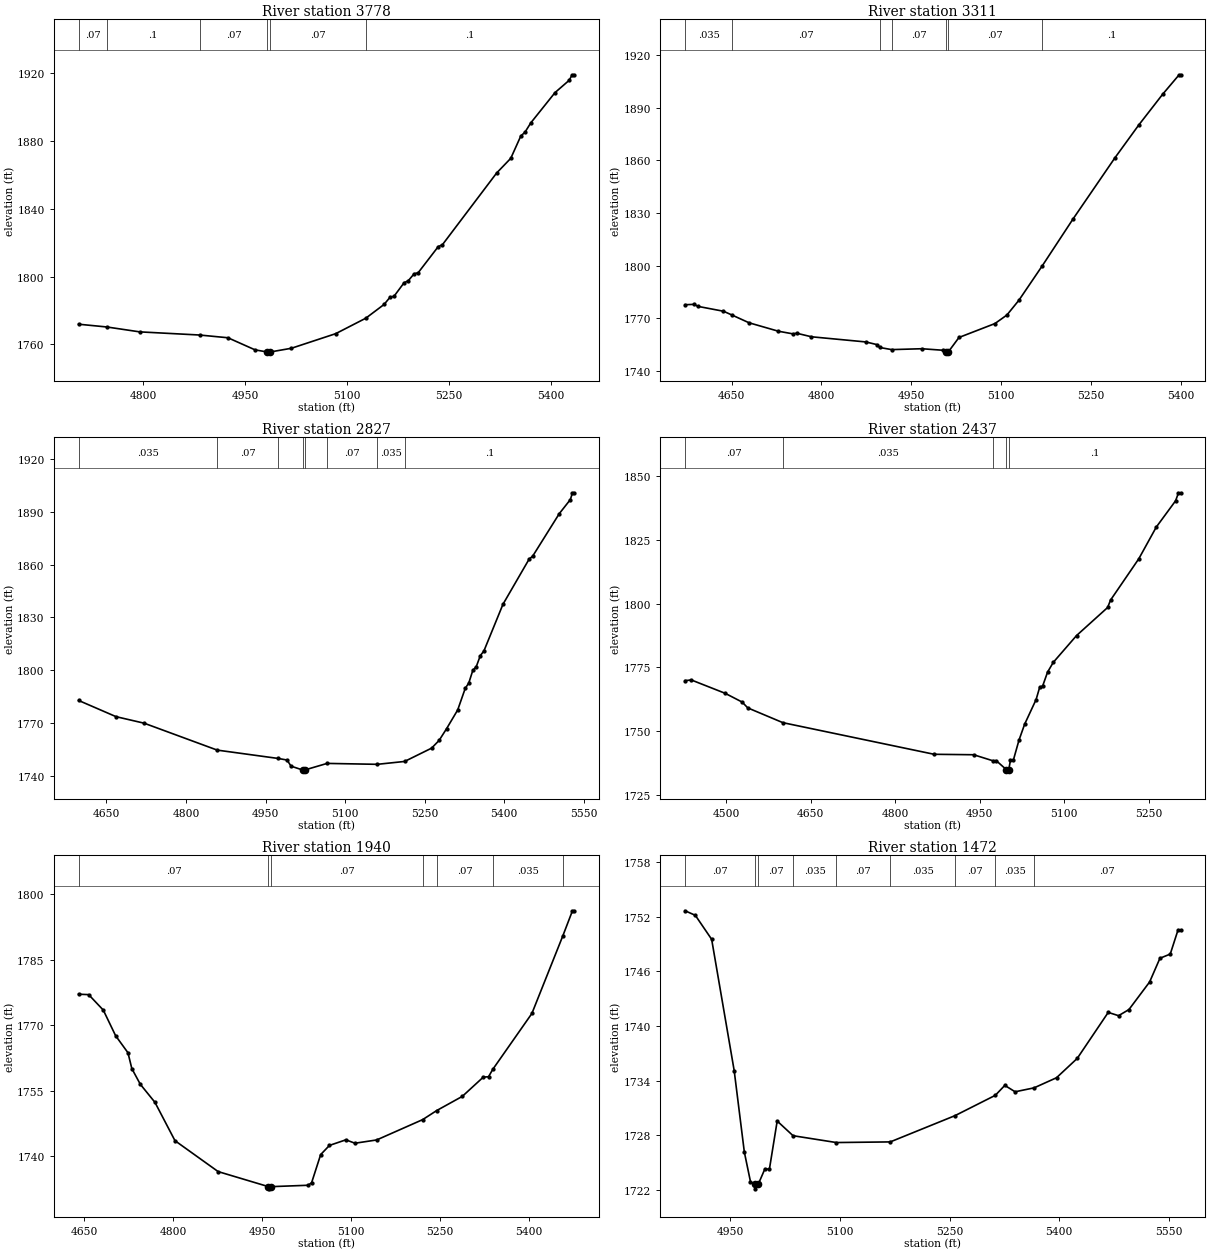
Type RM Length L Ch R = 1,3778,467,467,467
BEGIN DESCRIPTION:
Stream0074 7.0
END DESCRIPTION:
XS GIS Cut Line= 3
      1990775.00     13934575.03      1990775.00     13934275.00
      1990525.03     13933925.04
#Sta/Elev= 30
  4704.5 1771.96  4746.0 1770.33  4794.5 1767.44  4882.7 1765.58  4924.5 1763.96
  4964.5 1756.81  4982.5 1755.56  4982.7 1755.06  4986.6 1755.56  5018.0 1757.76
  5083.2 1766.37  5127.6 1775.51  5154.5 1783.62  5163.1 1787.79  5169.2 1788.47
  5184.0 1796.45  5190.1 1797.60  5198.7 1801.69  5204.8 1802.38  5234.3 1817.76
  5240.5 1818.90  5320.4 1861.25  5341.2 1869.92  5356.0 1883.11  5362.1 1885.31
  5370.7 1890.84  5406.4 1908.72  5427.3 1915.99  5431.6 1919.23  5434.6 1919.23
#Mann=6,-1,0
  4704.5    0.07       0  4746.0     0.1       0  4882.7    0.07       0
  4982.5    0.05       0  4986.6    0.07       0  5127.6     0.1       0
Bank Sta=4982.5,4986.6
Exp/Cntr=0.3,0.1

Type RM Length L Ch R = 1,3311,484,484,484
BEGIN DESCRIPTION:
Stream0074 6.0
END DESCRIPTION:
XS GIS Cut Line= 3
      1991375.01     13934625.02      1991225.00     13934225.00
      1991225.00     13933825.02
#Sta/Elev= 30
  4572.4 1777.76  4587.5 1777.98  4593.8 1776.83  4636.5 1774.05  4650.9 1771.86
  4679.2 1767.47  4728.2 1762.66  4753.1 1761.12  4758.4 1761.55  4783.3 1759.50
  4874.1 1756.56  4892.8 1755.03  4897.3 1753.40  4917.2 1752.19  4967.6 1752.69
  5002.1 1751.84  5007.5 1750.85  5007.8 1750.35  5011.7 1750.85  5029.6 1759.11
  5089.6 1767.03  5109.6 1771.90  5129.6 1780.31  5168.7 1799.98  5219.6 1826.44
  5289.6 1861.33  5329.6 1880.14  5369.6 1897.71  5397.1 1908.80  5399.6 1908.80
#Mann=7,-1,0
  4572.4   0.035       0  4650.9    0.07       0  4897.3   0.035       0
  4917.2    0.07       0  5007.5    0.05       0  5011.7    0.07       0
  5168.7     0.1       0
Bank Sta=5007.5,5011.7
Exp/Cntr=0.3,0.1

Type RM Length L Ch R = 1,2827,390,390,390
BEGIN DESCRIPTION:
Stream0074 5.0
END DESCRIPTION:
XS GIS Cut Line= 3
      1991725.00     13934625.02      1991675.00     13934225.00
      1991325.03     13933825.03
#Sta/Elev= 30
  4597.5 1782.86  4668.1 1773.66  4721.0 1769.96  4858.9 1754.67  4974.2 1749.92
  4990.6 1749.03  4998.1 1745.56  5019.8 1743.40  5020.1 1742.90  5024.1 1743.40
  5066.1 1747.12  5160.8 1746.60  5212.3 1748.23  5263.1 1755.77  5277.3 1760.14
  5291.5 1766.86  5312.4 1777.46  5326.7 1789.78  5333.3 1792.74  5340.9 1799.91
  5347.5 1802.10  5355.1 1808.33  5361.8 1810.93  5397.8 1837.48  5447.2 1863.16
  5453.8 1864.79  5504.1 1888.99  5525.0 1896.97  5528.8 1900.80  5532.1 1900.80
#Mann=8,-1,0
  4597.5   0.035       0  4858.9    0.07       0  4974.2   0.035       0
  5019.8   0.035       0  5024.1   0.035       0  5066.1    0.07       0
  5160.8   0.035       0  5212.3     0.1       0
Bank Sta=5019.8,5024.1
Exp/Cntr=0.3,0.1

Type RM Length L Ch R = 1,2437,497,497,497
BEGIN DESCRIPTION:
Stream0074 4.0
END DESCRIPTION:
XS GIS Cut Line= 3
      1991912.35     13934545.96      1991938.90     13933969.58
      1991888.28     13933672.45
#Sta/Elev= 30
  4427.7 1769.77  4438.7 1770.04  4498.7 1764.80  4528.8 1761.36  4538.8 1759.07
  4601.0 1753.27  4869.1 1740.85  4939.2 1740.67  4973.5 1738.29  4979.2 1738.35
  4997.1 1734.85  4997.4 1734.35  5001.4 1734.85  5004.5 1738.56  5009.6 1738.56
  5019.5 1746.37  5029.6 1752.68  5049.9 1762.35  5056.3 1767.22  5061.4 1767.60
  5070.2 1773.11  5080.3 1776.94  5121.6 1787.48  5176.7 1798.50  5181.8 1801.39
  5231.9 1817.62  5262.9 1830.07  5297.2 1840.42  5302.3 1843.55  5306.1 1843.55
#Mann=5,-1,0
  4427.7    0.07       0  4601.0   0.035       0  4973.5    0.07       0
  4997.1    0.05       0  5001.4     0.1       0
Bank Sta=4997.1,5001.4
Exp/Cntr=0.3,0.1

Type RM Length L Ch R = 1,1940,468,468,468
BEGIN DESCRIPTION:
Stream0074 3.0
END DESCRIPTION:
XS GIS Cut Line= 3
      1992475.01     13934425.02      1992375.00     13934075.00
      1992125.01     13933675.02
#Sta/Elev= 30
  4640.3 1777.08  4657.2 1776.99  4681.9 1773.44  4702.7 1767.57  4723.5 1763.67
  4730.0 1760.05  4744.3 1756.45  4769.0 1752.31  4802.8 1743.52  4875.6 1736.44
  4960.5 1732.99  4960.8 1732.49  4964.9 1732.99  5027.3 1733.31  5033.2 1733.89
  5048.5 1740.34  5063.3 1742.44  5091.0 1743.72  5106.3 1742.94  5142.9 1743.69
  5220.5 1748.35  5244.2 1750.43  5287.3 1753.67  5322.7 1758.08  5331.6 1758.18
  5338.8 1759.88  5404.7 1772.67  5457.1 1790.53  5473.1 1796.20  5476.0 1796.20
#Mann=7,-1,0
  4640.3    0.07       0  4960.5    0.05       0  4964.9    0.07       0
  5220.5   0.035       0  5244.2    0.07       0  5338.8   0.035       0
  5457.1    0.07       0
Bank Sta=4960.5,4964.9
Exp/Cntr=0.3,0.1

Type RM Length L Ch R = 1,1472,457,457,457
BEGIN DESCRIPTION:
Stream0074 2.0
END DESCRIPTION:
XS GIS Cut Line= 3
      1992875.00     13934124.99      1992825.00     13934025.00
      1992424.99     13933624.99
#Sta/Elev= 30
  4888.5 1752.63  4902.5 1752.13  4924.8 1749.50  4955.6 1735.10  4969.5 1726.15
  4977.9 1722.90  4984.1 1722.62  4984.4 1722.12  4988.5 1722.62  4997.5 1724.29
  5003.8 1724.29  5014.4 1729.56  5036.1 1727.95  5095.3 1727.20  5169.0 1727.27
  5257.5 1730.15  5312.6 1732.38  5325.6 1733.47  5339.7 1732.77  5365.6 1733.20
  5396.3 1734.31  5424.6 1736.43  5467.0 1741.48  5481.1 1741.12  5495.3 1741.79
  5523.6 1744.82  5537.7 1747.42  5551.8 1747.88  5562.4 1750.52  5566.0 1750.52
#Mann=9,-1,0
  4888.5    0.07       0  4984.1    0.05       0  4988.5    0.07       0
  5036.1   0.035       0  5095.3    0.07       0  5169.0   0.035       0
  5257.5    0.07       0  5312.6   0.035       0  5365.6    0.07       0
Bank Sta=4984.1,4988.5
Exp/Cntr=0.3,0.1

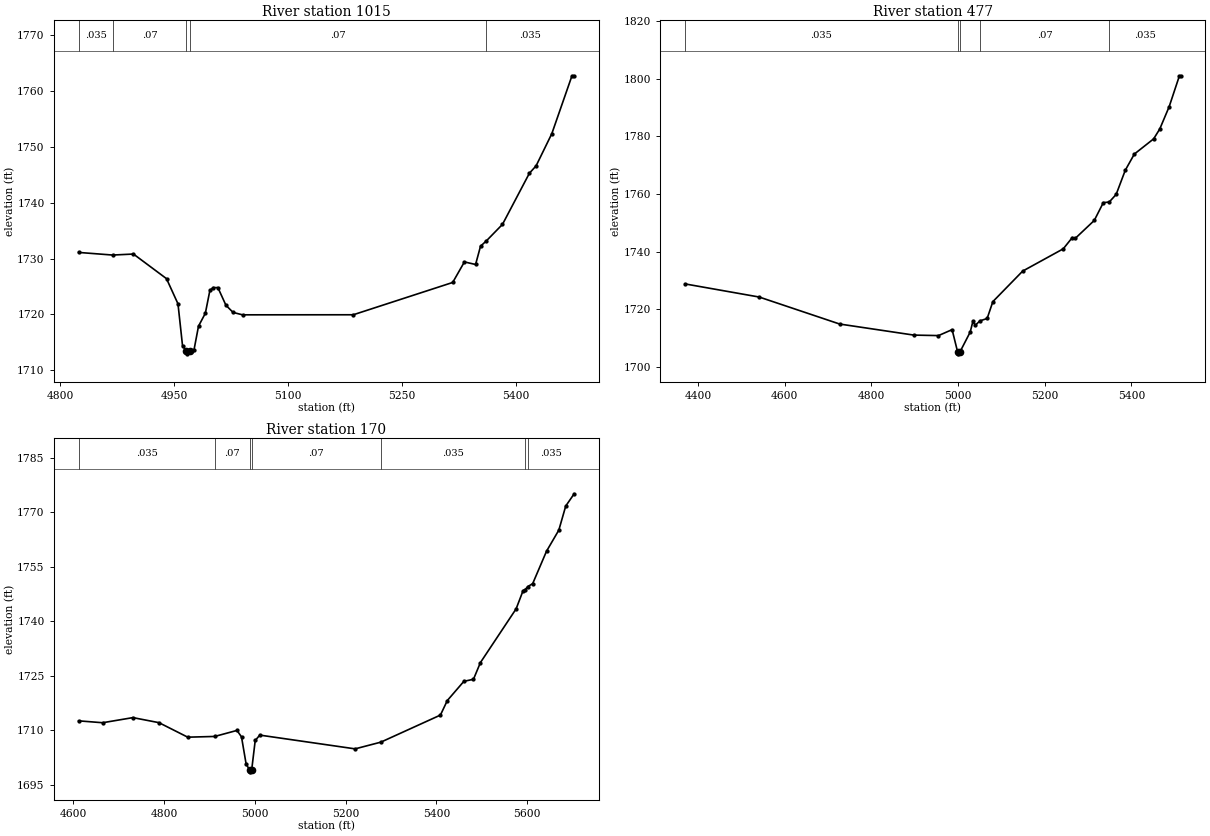
Type RM Length L Ch R = 1,1015,538,538,538
BEGIN DESCRIPTION:
Stream0074 1.0
END DESCRIPTION:
XS GIS Cut Line= 3
      1993074.98     13933774.97      1992975.00     13933625.00
      1992575.03     13933375.02
#Sta/Elev= 30
  4824.6 1731.12  4869.3 1730.65  4896.7 1730.83  4940.2 1726.42  4955.3 1721.91
  4961.3 1714.38  4966.5 1713.45  4966.9 1712.95  4971.0 1713.45  4976.3 1713.60
  4982.3 1717.91  4991.3 1720.22  4997.3 1724.33  5001.8 1724.82  5007.8 1724.82
  5018.4 1721.65  5027.8 1720.37  5040.2 1719.94  5185.9 1719.95  5316.7 1725.74
  5332.1 1729.42  5346.8 1728.96  5353.3 1732.23  5361.0 1733.19  5382.2 1736.15
  5417.6 1745.31  5426.4 1746.63  5447.1 1752.40  5473.6 1762.77  5476.5 1762.77
#Mann=5,-1,0
  4824.6   0.035       0  4869.3    0.07       0  4966.5    0.05       0
  4971.0    0.07       0  5361.0   0.035       0
Bank Sta=4966.5,4971
Exp/Cntr=0.3,0.1

Type RM Length L Ch R = 1,477,307,307,307
BEGIN DESCRIPTION:
Stream0074 0.0
END DESCRIPTION:
XS GIS Cut Line= 4
      1993133.97     13933790.97      1993257.63     13933303.86
      1993189.32     13933080.30      1992956.81     13932745.43
#Sta/Elev= 30
  4369.8 1728.78  4541.0 1724.22  4726.7 1714.84  4897.9 1711.00  4954.8 1710.83
  4986.2 1712.90  4999.2 1704.99  4999.5 1704.49  5003.8 1704.99  5028.0 1712.06
  5034.3 1715.82  5039.5 1714.39  5050.6 1715.95  5067.1 1716.77  5080.3 1722.63
  5149.1 1733.23  5242.8 1740.97  5263.7 1744.89  5270.8 1744.64  5314.4 1750.83
  5335.3 1757.02  5349.0 1757.23  5365.0 1759.89  5386.0 1768.27  5406.9 1773.89
  5451.5 1779.18  5465.6 1782.60  5487.3 1790.35  5511.0 1801.09  5513.8 1801.09
#Mann=5,-1,0
  4369.8   0.035       0  4999.2   0.035       0  5003.8   0.035       0
  5050.6    0.07       0  5349.0   0.035       0
Bank Sta=4999.2,5003.8
Exp/Cntr=0.3,0.1

Type RM Length L Ch R = 1,170,0,0,0
BEGIN DESCRIPTION:
Stream0074 0.1
END DESCRIPTION:
XS GIS Cut Line= 5
      1993342.33     13933516.02      1993503.91     13933265.34
      1993483.15     13933070.17      1993477.72     13932963.51
      1993063.62     13932700.46
#Sta/Elev= 30
  4611.5 1712.56  4664.4 1712.04  4731.1 1713.45  4788.5 1712.06  4851.9 1708.06
  4911.3 1708.26  4960.4 1709.92  4970.4 1708.14  4980.5 1700.70  4988.2 1699.01
  4988.5 1698.51  4992.8 1699.01  5000.6 1707.15  5010.7 1708.63  5220.7 1704.84
  5277.4 1706.69  5408.7 1714.15  5423.9 1718.16  5460.4 1723.45  5481.5 1724.01
  5496.8 1728.61  5575.5 1743.42  5590.8 1748.42  5594.8 1748.66  5601.4 1749.56
  5612.0 1750.37  5642.5 1759.30  5669.6 1765.11  5684.8 1771.74  5703.4 1775.12
#Mann=7,-1,0
  4611.5   0.035       0  4911.3    0.07       0  4988.2    0.05       0
  4992.8    0.07       0  5277.4   0.035       0  5594.8    0.07       0
  5601.4   0.035       0
Bank Sta=4988.2,4992.8
Exp/Cntr=0.3,0.1

Chan Stop Cuts=-1