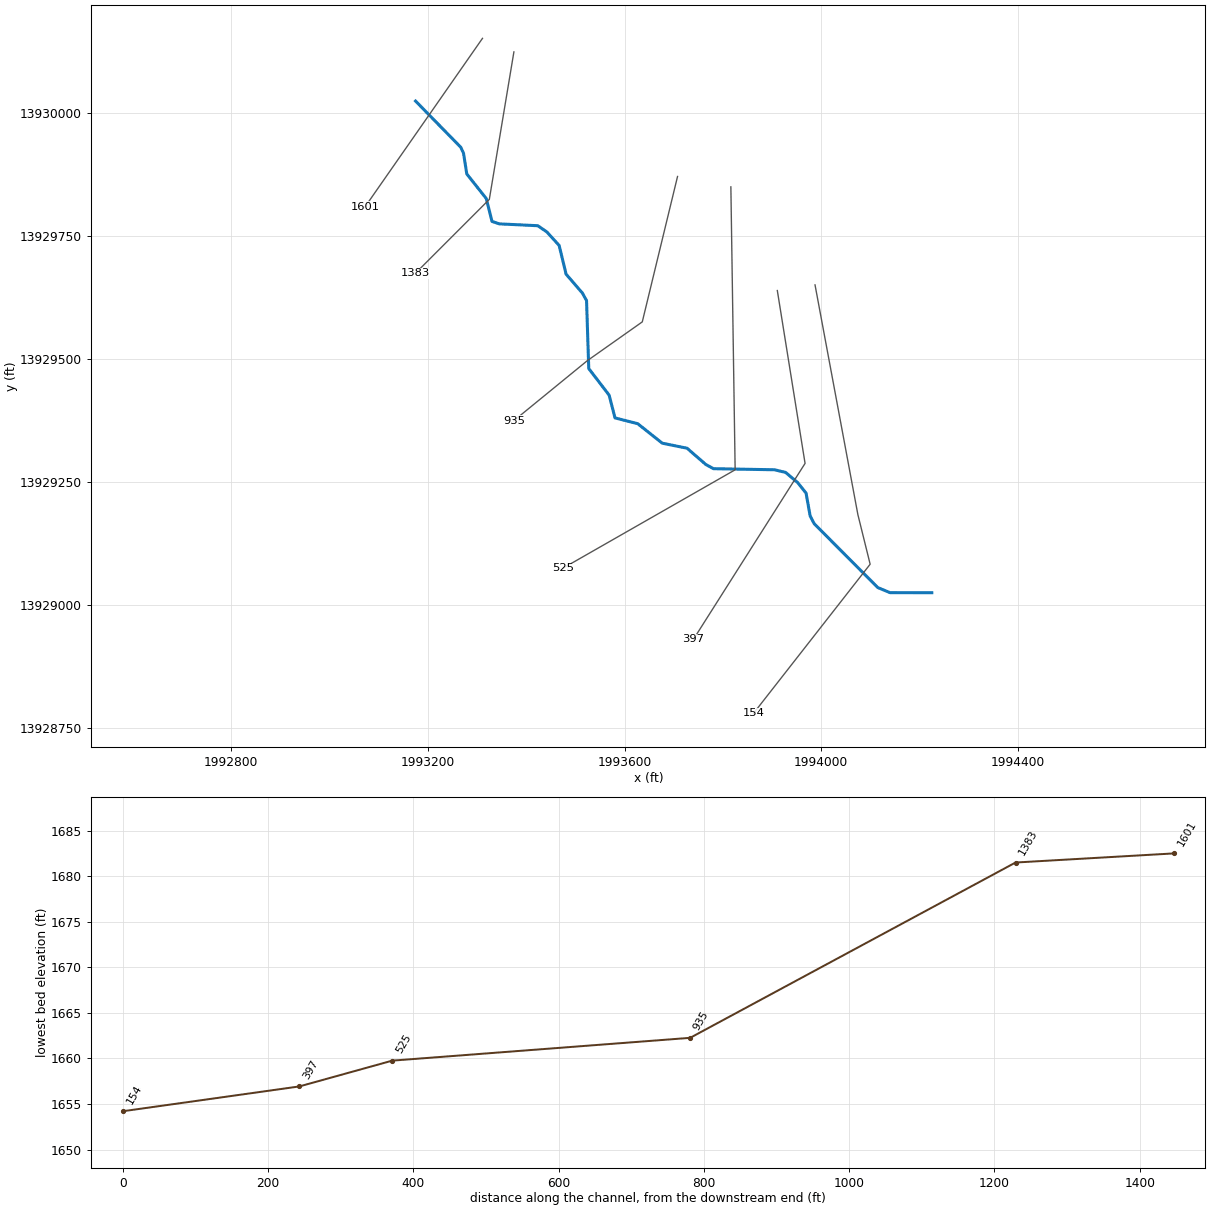
--- Stream0075.prj (project) ---

Proj Title=Stream0075 Base Level Engineering
Current Plan=p01
Default Exp/Contr=0.3,0.1
English Units
Geom File=g01
Flow File=f01
Plan File=p01
BEGIN DESCRIPTION:
Stream0075
END DESCRIPTION:

--- Stream0075.p01 (plan) ---

Plan Title=Multiple Run
Short Identifier=Multiple
Geom File=g01
Flow File=f01
Subcritical Flow
K Sum by GR= 0
Std Step Tol= 0.01
Critical Tol= 0.01
Num of Std Step Trials= 20
Max Error Tol= 0.3
Flow Tol Ratio= 0.001
Split Flow NTrial= 30
Split Flow Tol= 0.02
Split Flow Ratio= 0.02
Log Output Level= 0
Friction Slope Method= 1
Unsteady Friction Slope Method= 2
Unsteady Bridges Friction Slope Method= 1
Parabolic Critical Depth
Global Vel Dist=  1 , 1 , 1
Global Log Level= 0
CheckData=True
Encroach Param= -1, 0, 0, 0
BEGIN DESCRIPTION:
Multiple Run
END DESCRIPTION:

--- Stream0075.f01 (steady flow) ---

Flow Title=Multiple
Number of Profiles=7
Profile Names=10-year,25-year,50-year,1pct_min,100-year,1pct_plu,500-year
River Rch & RM= Stream0075,Reach-1,1601
    1042    1798    2530    1728    3448    6880    6352
Boundary for River Rch & Prof#=Stream0075,Reach-1,1
Up Type=0
Dn Type=3
Dn Slope=0.005
Boundary for River Rch & Prof#=Stream0075,Reach-1,2
Up Type=0
Dn Type=3
Dn Slope=0.005
Boundary for River Rch & Prof#=Stream0075,Reach-1,3
Up Type=0
Dn Type=3
Dn Slope=0.005
Boundary for River Rch & Prof#=Stream0075,Reach-1,4
Up Type=0
Dn Type=3
Dn Slope=0.005
Boundary for River Rch & Prof#=Stream0075,Reach-1,5
Up Type=0
Dn Type=3
Dn Slope=0.005
Boundary for River Rch & Prof#=Stream0075,Reach-1,6
Up Type=0
Dn Type=3
Dn Slope=0.005
Boundary for River Rch & Prof#=Stream0075,Reach-1,7
Up Type=0
Dn Type=3
Dn Slope=0.005

--- Stream0075.g01 (geometry) ---

Geom Title=Existing Conditions

River Reach=Stream0075,Reach-1
Reach XY= 30
      1993175.00     13930025.00      1993266.91     13929931.08
      1993272.51     13929918.97      1993279.17     13929876.70
      1993318.74     13929826.80      1993330.45     13929780.25
      1993345.26     13929775.22      1993423.65     13929771.45
      1993442.11     13929758.69      1993466.99     13929731.38
      1993481.15     13929672.86      1993514.20     13929634.67
      1993522.75     13929619.07      1993527.24     13929480.91
      1993568.72     13929426.84      1993580.58     13929380.58
      1993626.85     13929368.76      1993676.69     13929329.15
      1993727.18     13929318.88      1993765.33     13929285.80
      1993780.93     13929277.25      1993905.11     13929275.07
      1993927.70     13929269.64      1993952.19     13929248.96
      1993969.26     13929227.57      1993977.55     13929181.09
      1993985.79     13929165.34      1994115.18     13929035.43
      1994140.05     13929025.12      1994225.00     13929025.00

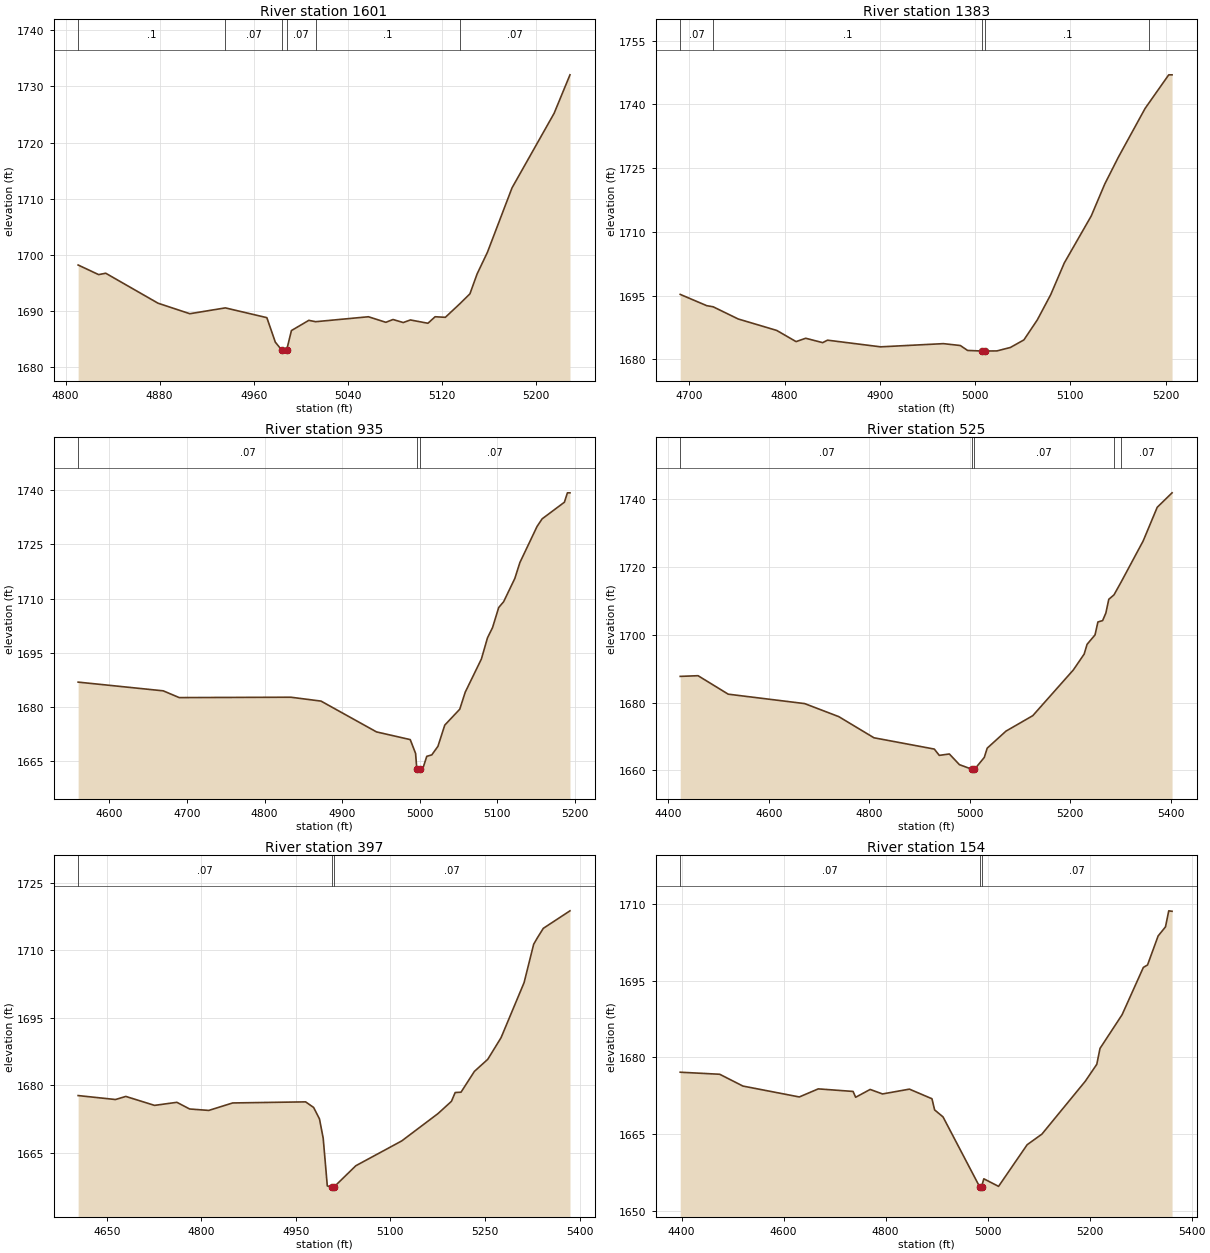
Type RM Length L Ch R = 1,1601,218,218,218
BEGIN DESCRIPTION:
Stream0075 4.0
END DESCRIPTION:
XS GIS Cut Line= 2
      1993311.11     13930152.58      1993071.93     13929809.41
#Sta/Elev= 30
  4810.7 1698.19  4828.1 1696.48  4834.2 1696.72  4878.7 1691.38  4905.7 1689.51
  4935.9 1690.55  4971.2 1688.81  4978.4 1684.45  4984.0 1682.99  4984.3 1682.49
  4987.8 1682.49  4988.0 1682.99  4992.1 1686.51  5006.9 1688.33  5012.7 1688.09
  5057.6 1688.97  5072.4 1687.98  5078.5 1688.48  5087.2 1687.94  5093.3 1688.40
  5108.2 1687.81  5114.3 1688.97  5123.0 1688.87  5135.2 1691.26  5143.9 1693.05
  5150.0 1696.59  5158.8 1700.46  5179.7 1711.93  5215.5 1725.21  5229.0 1732.07
#Mann=6,-1,0
  4810.7     0.1       0  4935.9    0.07       0  4984.0    0.05       0
  4988.0    0.07       0  5012.7     0.1       0  5135.2    0.07       0
Bank Sta=4984,4988
Exp/Cntr=0.3,0.1

Type RM Length L Ch R = 1,1383,448,448,448
BEGIN DESCRIPTION:
Stream0075 3.0
END DESCRIPTION:
XS GIS Cut Line= 3
      1993374.99     13930124.96      1993325.00     13929825.00
      1993175.02     13929675.02
#Sta/Elev= 30
  4690.5 1695.31  4718.3 1692.66  4725.1 1692.39  4751.3 1689.53  4791.8 1686.83
  4812.1 1684.20  4822.2 1684.99  4840.0 1683.96  4845.1 1684.54  4900.8 1682.97
  4966.7 1683.72  4984.5 1683.28  4992.1 1682.12  5006.7 1681.99  5007.0 1681.49
  5010.5 1681.49  5010.7 1681.99  5022.9 1682.01  5037.0 1682.82  5051.2 1684.60
  5065.3 1689.32  5079.4 1695.28  5093.6 1702.71  5121.9 1713.78  5136.0 1721.25
  5150.2 1727.54  5178.4 1739.07  5182.9 1740.51  5203.2 1746.98  5206.7 1746.98
#Mann=5,-1,0
  4690.5    0.07       0  4725.1     0.1       0  5006.7    0.05       0
  5010.7     0.1       0  5182.9    0.07       0
Bank Sta=5006.7,5010.7
Exp/Cntr=0.3,0.1

Type RM Length L Ch R = 1,935,410,410,410
BEGIN DESCRIPTION:
Stream0075 2.0
END DESCRIPTION:
XS GIS Cut Line= 4
      1993707.84     13929871.61      1993636.11     13929575.85
      1993524.21     13929496.87      1993374.97     13929374.97
#Sta/Elev= 30
  4559.6 1686.88  4669.3 1684.47  4689.9 1682.60  4833.9 1682.70  4872.7 1681.63
  4944.2 1673.11  4987.7 1670.98  4994.6 1667.15  4996.2 1662.76  4996.4 1662.26
  5000.2 1662.76  5003.6 1662.76  5009.0 1666.35  5015.5 1666.76  5023.4 1669.12
  5032.2 1674.99  5051.5 1679.38  5058.6 1684.11  5079.4 1693.27  5087.3 1699.15
  5093.8 1701.97  5101.7 1707.50  5108.1 1709.13  5122.5 1715.55  5129.0 1719.94
  5151.2 1729.95  5157.7 1732.04  5186.4 1736.64  5190.3 1739.24  5193.6 1739.24
#Mann=3,-1,0
  4559.6    0.07       0  4996.2    0.05       0  5000.2    0.07       0
Bank Sta=4996.2,5000.2
Exp/Cntr=0.3,0.1

Type RM Length L Ch R = 1,525,128,128,128
BEGIN DESCRIPTION:
Stream0075 1.0
END DESCRIPTION:
XS GIS Cut Line= 3
      1993816.30     13929850.46      1993825.00     13929275.00
      1993475.03     13929075.02
#Sta/Elev= 30
  4423.8 1687.72  4459.3 1687.92  4519.3 1682.47  4671.4 1679.69  4739.3 1675.84
  4809.3 1669.60  4929.3 1666.27  4939.3 1664.41  4959.3 1664.82  4979.3 1661.67
  5005.2 1660.26  5005.5 1659.76  5009.2 1660.26  5028.8 1663.81  5034.6 1666.54
  5072.0 1671.57  5125.3 1676.13  5205.9 1689.61  5227.5 1694.30  5233.3 1697.18
  5249.1 1699.96  5254.9 1703.78  5264.2 1704.18  5270.7 1706.43  5276.5 1710.47
  5286.8 1711.77  5301.0 1715.55  5344.9 1727.69  5372.9 1737.63  5402.4 1741.89
#Mann=5,-1,0
  4423.8    0.07       0  5005.2    0.05       0  5009.2    0.07       0
  5286.8   0.035       0  5301.0    0.07       0
Bank Sta=5005.2,5009.2
Exp/Cntr=0.3,0.1

Type RM Length L Ch R = 1,397,243,243,243
BEGIN DESCRIPTION:
Stream0075 0.1
END DESCRIPTION:
XS GIS Cut Line= 3
      1993910.78     13929639.61      1993967.21     13929288.03
      1993740.05     13928929.99
#Sta/Elev= 30
  4604.7 1677.71  4664.0 1676.83  4680.3 1677.52  4725.9 1675.53  4761.3 1676.21
  4781.5 1674.73  4811.9 1674.41  4849.8 1676.07  4965.5 1676.31  4978.2 1675.07
  4987.5 1672.52  4993.4 1668.22  4999.9 1657.64  5006.7 1657.43  5006.9 1656.93
  5010.7 1657.43  5045.1 1662.12  5118.0 1667.64  5175.6 1673.72  5196.8 1676.43
  5202.7 1678.38  5212.0 1678.46  5233.2 1683.08  5254.4 1685.76  5275.5 1690.57
  5312.0 1702.79  5327.2 1711.31  5333.2 1712.77  5342.5 1714.85  5384.8 1718.74
#Mann=3,-1,0
  4604.7    0.07       0  5006.7    0.05       0  5010.7    0.07       0
Bank Sta=5006.7,5010.7
Exp/Cntr=0.3,0.1

Type RM Length L Ch R = 1,154,0,0,0
BEGIN DESCRIPTION:
Stream0075 0.0
END DESCRIPTION:
XS GIS Cut Line= 4
      1993987.47     13929651.10      1994074.63     13929183.86
      1994099.59     13929082.95      1993862.30     13928779.58
#Sta/Elev= 30
  4397.2 1677.08  4474.6 1676.68  4520.2 1674.37  4630.7 1672.24  4667.9 1673.82
  4736.1 1673.32  4741.2 1672.18  4769.6 1673.71  4793.9 1672.83  4846.6 1673.77
  4890.8 1671.89  4896.0 1669.71  4912.5 1668.34  4984.1 1654.71  4984.4 1654.21
  4988.1 1654.71  4992.5 1656.23  5021.4 1654.75  5077.5 1662.90  5106.4 1664.97
  5191.4 1675.31  5214.0 1678.63  5220.3 1681.73  5263.7 1688.34  5305.3 1697.58
  5313.5 1698.06  5334.3 1703.74  5348.7 1705.51  5355.1 1708.65  5361.6 1708.56
#Mann=3,-1,0
  4397.2    0.07       0  4984.1    0.05       0  4988.1    0.07       0
Bank Sta=4984.1,4988.1
Exp/Cntr=0.3,0.1

Chan Stop Cuts=-1