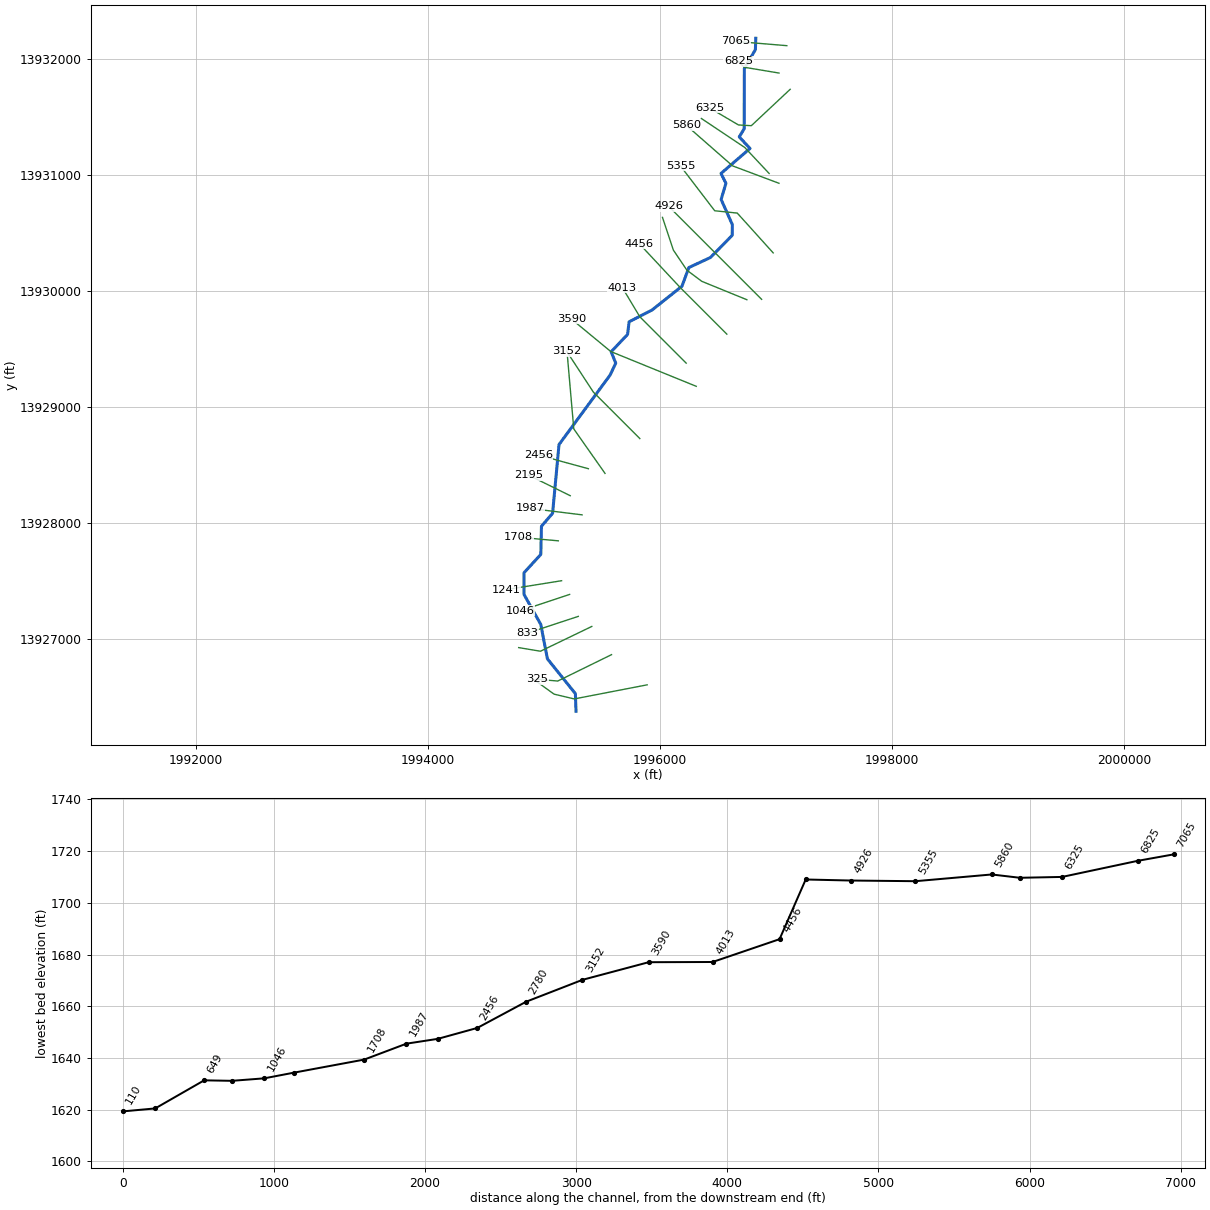
--- Stream0076.prj (project) ---

Proj Title=Stream0076 Base Level Engineering
Current Plan=p01
Default Exp/Contr=0.3,0.1
English Units
Geom File=g01
Flow File=f01
Plan File=p01
BEGIN DESCRIPTION:
Stream0076
END DESCRIPTION:

--- Stream0076.p01 (plan) ---

Plan Title=Multiple Run
Short Identifier=Multiple
Geom File=g01
Flow File=f01
Subcritical Flow
K Sum by GR= 0
Std Step Tol= 0.01
Critical Tol= 0.01
Num of Std Step Trials= 20
Max Error Tol= 0.3
Flow Tol Ratio= 0.001
Split Flow NTrial= 30
Split Flow Tol= 0.02
Split Flow Ratio= 0.02
Log Output Level= 0
Friction Slope Method= 1
Unsteady Friction Slope Method= 2
Unsteady Bridges Friction Slope Method= 1
Parabolic Critical Depth
Global Vel Dist=  1 , 1 , 1
Global Log Level= 0
CheckData=True
Encroach Param= -1, 0, 0, 0
BEGIN DESCRIPTION:
Multiple Run
END DESCRIPTION:

--- Stream0076.f01 (steady flow) ---

Flow Title=Multiple
Number of Profiles=7
Profile Names=10-year,25-year,50-year,1pct_min,100-year,1pct_plu,500-year
River Rch & RM= Stream0076,Reach-1,7065
     997    1715    2408    1642    3277    6538    6016
River Rch & RM= Stream0076,Reach-1,6046
    1366    2385    3381    2324    4637    9252    8655
Boundary for River Rch & Prof#=Stream0076,Reach-1,1
Up Type=0
Dn Type=3
Dn Slope=0.005
Boundary for River Rch & Prof#=Stream0076,Reach-1,2
Up Type=0
Dn Type=3
Dn Slope=0.005
Boundary for River Rch & Prof#=Stream0076,Reach-1,3
Up Type=0
Dn Type=3
Dn Slope=0.005
Boundary for River Rch & Prof#=Stream0076,Reach-1,4
Up Type=0
Dn Type=3
Dn Slope=0.005
Boundary for River Rch & Prof#=Stream0076,Reach-1,5
Up Type=0
Dn Type=3
Dn Slope=0.005
Boundary for River Rch & Prof#=Stream0076,Reach-1,6
Up Type=0
Dn Type=3
Dn Slope=0.005
Boundary for River Rch & Prof#=Stream0076,Reach-1,7
Up Type=0
Dn Type=3
Dn Slope=0.005

--- Stream0076.g01 (geometry) ---

Geom Title=Existing Conditions

River Reach=Stream0076,Reach-1
Reach XY= 30
      1996825.00     13932175.00      1996821.37     13932076.50
      1996726.20     13931914.50      1996724.81     13931394.98
      1996682.23     13931324.89      1996775.00     13931225.00
      1996524.96     13931009.76      1996567.40     13930925.01
      1996526.11     13930785.55      1996622.84     13930569.02
      1996621.54     13930476.50      1996434.68     13930285.76
      1996247.72     13930198.90      1996188.63     13930038.46
      1995931.06     13929833.14      1995732.75     13929731.46
      1995719.47     13929622.58      1995578.16     13929473.35
      1995617.44     13929375.00      1995569.19     13929272.71
      1995128.54     13928673.54      1995072.93     13928080.86
      1994977.07     13927969.14      1994971.46     13927726.46
      1994827.06     13927569.15      1994827.24     13927380.93
      1994971.24     13927123.44      1995028.62     13926826.50
      1995269.56     13926527.46      1995275.00     13926375.00

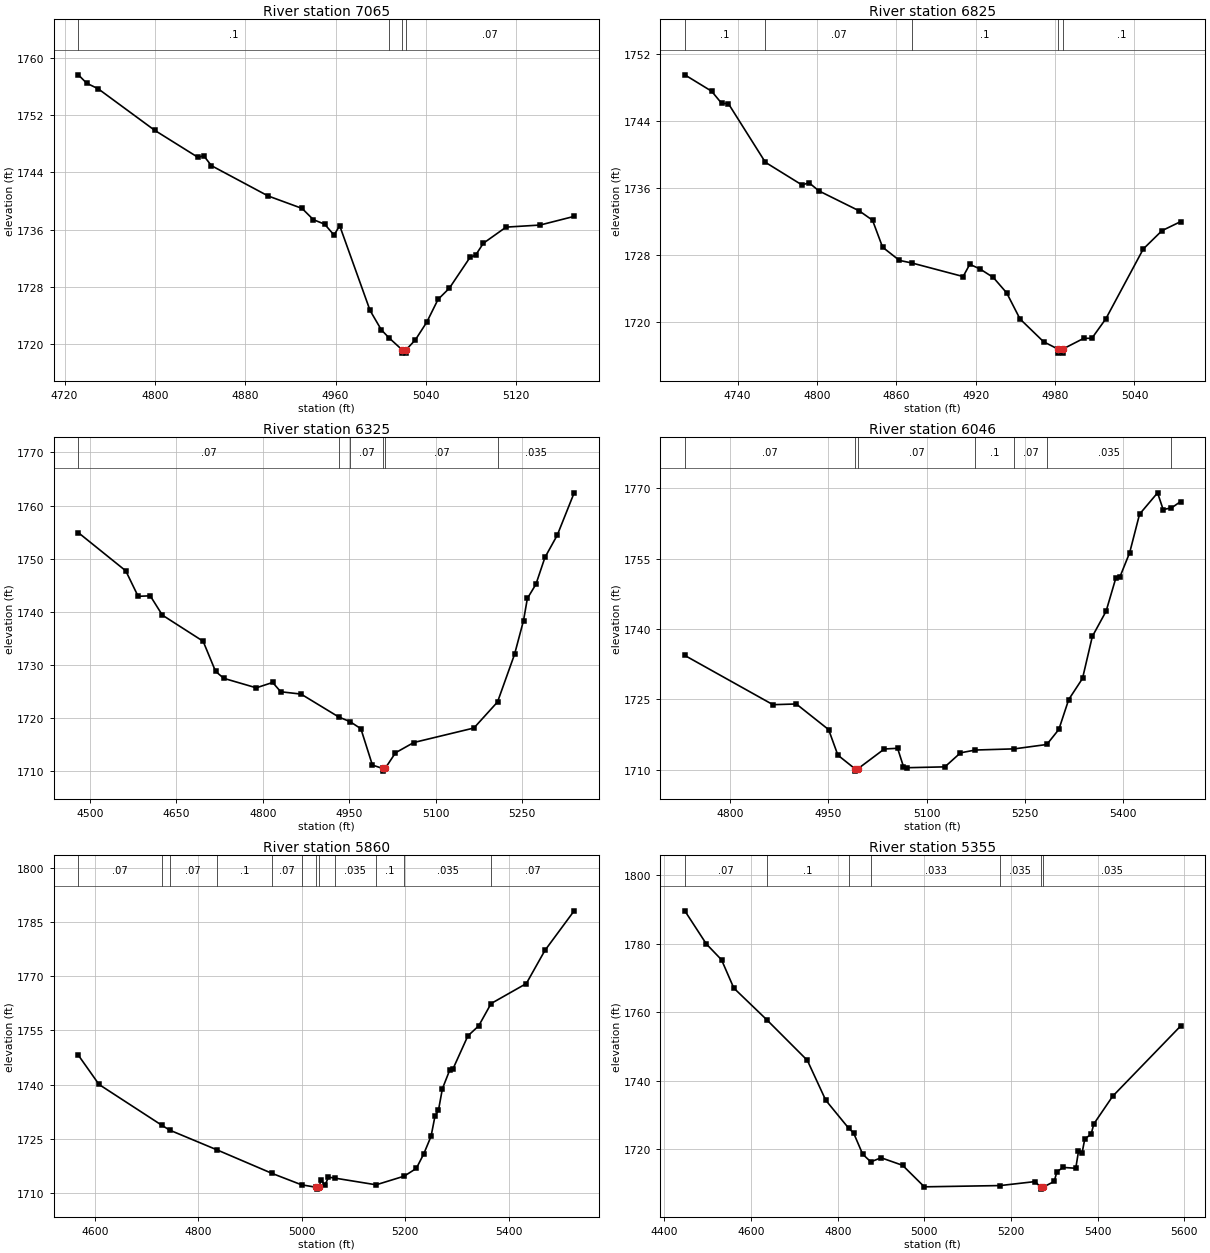
Type RM Length L Ch R = 1,7065,240,240,240
BEGIN DESCRIPTION:
Stream0076 16.0
END DESCRIPTION:
XS GIS Cut Line= 2
      1997092.39     13932110.93      1996654.91     13932147.39
#Sta/Elev= 30
  4732.2 1757.61  4739.6 1756.44  4749.7 1755.67  4799.8 1749.87  4838.2 1746.09
  4843.2 1746.33  4850.0 1744.94  4900.2 1740.71  4930.3 1738.97  4940.3 1737.40
  4950.3 1736.77  4958.6 1735.25  4963.6 1736.56  4990.5 1724.73  5000.5 1722.02
  5007.5 1720.88  5018.6 1719.28  5018.8 1718.78  5022.3 1718.78  5022.6 1719.28
  5030.6 1720.63  5040.7 1723.10  5050.7 1726.28  5060.7 1727.84  5079.0 1732.14
  5084.0 1732.46  5090.8 1734.11  5110.9 1736.36  5141.0 1736.65  5171.2 1737.86
#Mann=4,-1,0
  4732.2     0.1       0  5007.5    0.07       0  5018.6    0.05       0
  5022.6    0.07       0
Bank Sta=5018.6,5022.6
Exp/Cntr=0.3,0.1

Type RM Length L Ch R = 1,6825,500,500,500
BEGIN DESCRIPTION:
Stream0076 15.0
END DESCRIPTION:
XS GIS Cut Line= 3
      1997025.00     13931875.00      1996725.00     13931925.00
      1996675.03     13931974.97
#Sta/Elev= 30
  4700.1 1749.51  4720.4 1747.55  4728.0 1746.09  4733.0 1746.08  4761.0 1739.06
  4788.8 1736.34  4793.9 1736.63  4801.5 1735.64  4831.9 1733.26  4842.0 1732.14
  4849.6 1728.92  4862.3 1727.34  4872.0 1727.02  4910.5 1725.41  4915.5 1726.87
  4923.1 1726.33  4933.3 1725.30  4943.4 1723.46  4953.5 1720.34  4971.3 1717.62
  4982.0 1716.76  4982.2 1716.26  4985.7 1716.26  4986.0 1716.76  5001.7 1718.03
  5007.8 1718.03  5018.4 1720.37  5046.7 1728.71  5060.8 1730.89  5074.9 1731.97
#Mann=5,-1,0
  4700.1     0.1       0  4761.0    0.07       0  4872.0     0.1       0
  4982.0    0.05       0  4986.0     0.1       0
Bank Sta=4982,4986
Exp/Cntr=0.3,0.1

Type RM Length L Ch R = 1,6325,279,279,279
BEGIN DESCRIPTION:
Stream0076 14.0
END DESCRIPTION:
XS GIS Cut Line= 4
      1997121.42     13931734.99      1996786.52     13931421.33
      1996675.52     13931427.74      1996425.02     13931574.99
#Sta/Elev= 30
  4479.9 1754.90  4562.2 1747.72  4583.7 1742.92  4604.7 1743.02  4625.7 1739.39
  4696.5 1734.47  4718.0 1728.83  4732.2 1727.50  4788.8 1725.71  4817.2 1726.72
  4831.2 1724.97  4866.5 1724.53  4931.8 1720.23  4951.6 1719.34  4970.3 1718.02
  4990.3 1711.18  5008.4 1710.54  5008.6 1710.04  5012.4 1710.54  5030.4 1713.49
  5062.1 1715.42  5166.5 1718.15  5207.5 1723.05  5237.0 1732.00  5252.6 1738.36
  5259.3 1742.53  5274.1 1745.18  5289.8 1750.24  5311.2 1754.43  5340.5 1762.39
#Mann=6,-1,0
  4479.9    0.07       0  4931.8     0.1       0  4951.6    0.07       0
  5008.4    0.05       0  5012.4    0.07       0  5207.5   0.035       0
Bank Sta=5008.4,5012.4
Exp/Cntr=0.3,0.1

Type RM Length L Ch R = 1,6046,186,186,186
BEGIN DESCRIPTION:
Mapping XS 909cd92a
END DESCRIPTION:
XS GIS Cut Line= 3
      1996939.94     13931009.55      1996729.89     13931233.47
      1996355.76     13931483.48
#Sta/Elev= 30
  4730.9 1734.38  4865.5 1723.88  4901.1 1724.03  4950.5 1718.56  4964.6 1713.12
  4990.7 1710.21  4991.1 1709.71  4995.2 1710.21  5035.5 1714.43  5055.8 1714.58
  5064.8 1710.65  5070.8 1710.44  5128.0 1710.62  5151.8 1713.61  5174.4 1714.21
  5234.2 1714.46  5283.6 1715.39  5302.0 1718.61  5317.0 1724.97  5338.1 1729.47
  5353.1 1738.43  5374.1 1743.81  5389.1 1750.94  5395.1 1751.09  5410.1 1756.30
  5425.2 1764.51  5452.7 1769.06  5461.2 1765.50  5473.9 1765.84  5487.9 1767.20
#Mann=7,-1,0
  4730.9    0.07       0  4990.7    0.05       0  4995.2    0.07       0
  5174.4     0.1       0  5234.2    0.07       0  5283.6   0.035       0
  5473.9    0.07       0
Bank Sta=4990.7,4995.2
Exp/Cntr=0.3,0.1

Type RM Length L Ch R = 1,5860,505,505,505
BEGIN DESCRIPTION:
Stream0076 13.0
END DESCRIPTION:
XS GIS Cut Line= 3
      1997024.98     13930925.01      1996625.00     13931075.00
      1996224.99     13931425.01
#Sta/Elev= 30
  4567.8 1748.15  4607.8 1740.03  4729.3 1728.70  4744.4 1727.36  4835.8 1721.89
  4942.4 1715.35  4999.4 1712.19  5028.3 1711.49  5028.6 1710.99  5032.8 1711.49
  5037.2 1713.49  5044.8 1712.13  5051.5 1714.31  5063.2 1714.06  5143.6 1712.19
  5197.9 1714.59  5221.3 1716.74  5235.6 1720.74  5249.8 1725.64  5257.4 1731.23
  5264.1 1732.84  5271.7 1738.83  5285.9 1744.02  5292.5 1744.44  5321.0 1753.50
  5341.9 1756.28  5365.9 1762.48  5434.0 1768.02  5470.0 1777.22  5526.5 1788.20
#Mann=12,-1,0
  4567.8    0.07       0  4729.3     0.1       0  4744.4    0.07       0
  4835.8     0.1       0  4942.4    0.07       0  4999.4     0.1       0
  5028.3    0.05       0  5032.8     0.1       0  5063.2   0.035       0
  5143.6     0.1       0  5197.9   0.035       0  5365.9    0.07       0
Bank Sta=5028.3,5032.8
Exp/Cntr=0.3,0.1

Type RM Length L Ch R = 1,5355,429,429,429
BEGIN DESCRIPTION:
Stream0076 12.0
END DESCRIPTION:
XS GIS Cut Line= 4
      1996974.99     13930325.02      1996665.19     13930668.24
      1996470.90     13930688.14      1996175.01     13931074.99
#Sta/Elev= 30
  4447.0 1789.59  4496.7 1779.93  4531.8 1775.30  4560.2 1767.04  4635.8 1757.86
  4729.9 1745.96  4772.4 1734.33  4825.2 1726.18  4836.7 1724.77  4857.6 1718.60
  4876.4 1716.35  4900.2 1717.54  4949.8 1715.34  5000.0 1709.06  5175.3 1709.43
  5256.2 1710.60  5268.4 1708.89  5268.7 1708.39  5273.0 1708.89  5299.8 1710.63
  5306.1 1713.48  5320.6 1714.72  5349.6 1714.48  5355.9 1719.41  5364.2 1718.96
  5370.5 1723.08  5385.0 1724.38  5391.3 1727.41  5434.8 1735.49  5591.7 1755.98
#Mann=7,-1,0
  4447.0    0.07       0  4635.8     0.1       0  4825.2   0.035       0
  4876.4   0.033       0  5175.3   0.035       0  5268.4   0.033       0
  5273.0   0.035       0
Bank Sta=5268.4,5273
Exp/Cntr=0.3,0.1

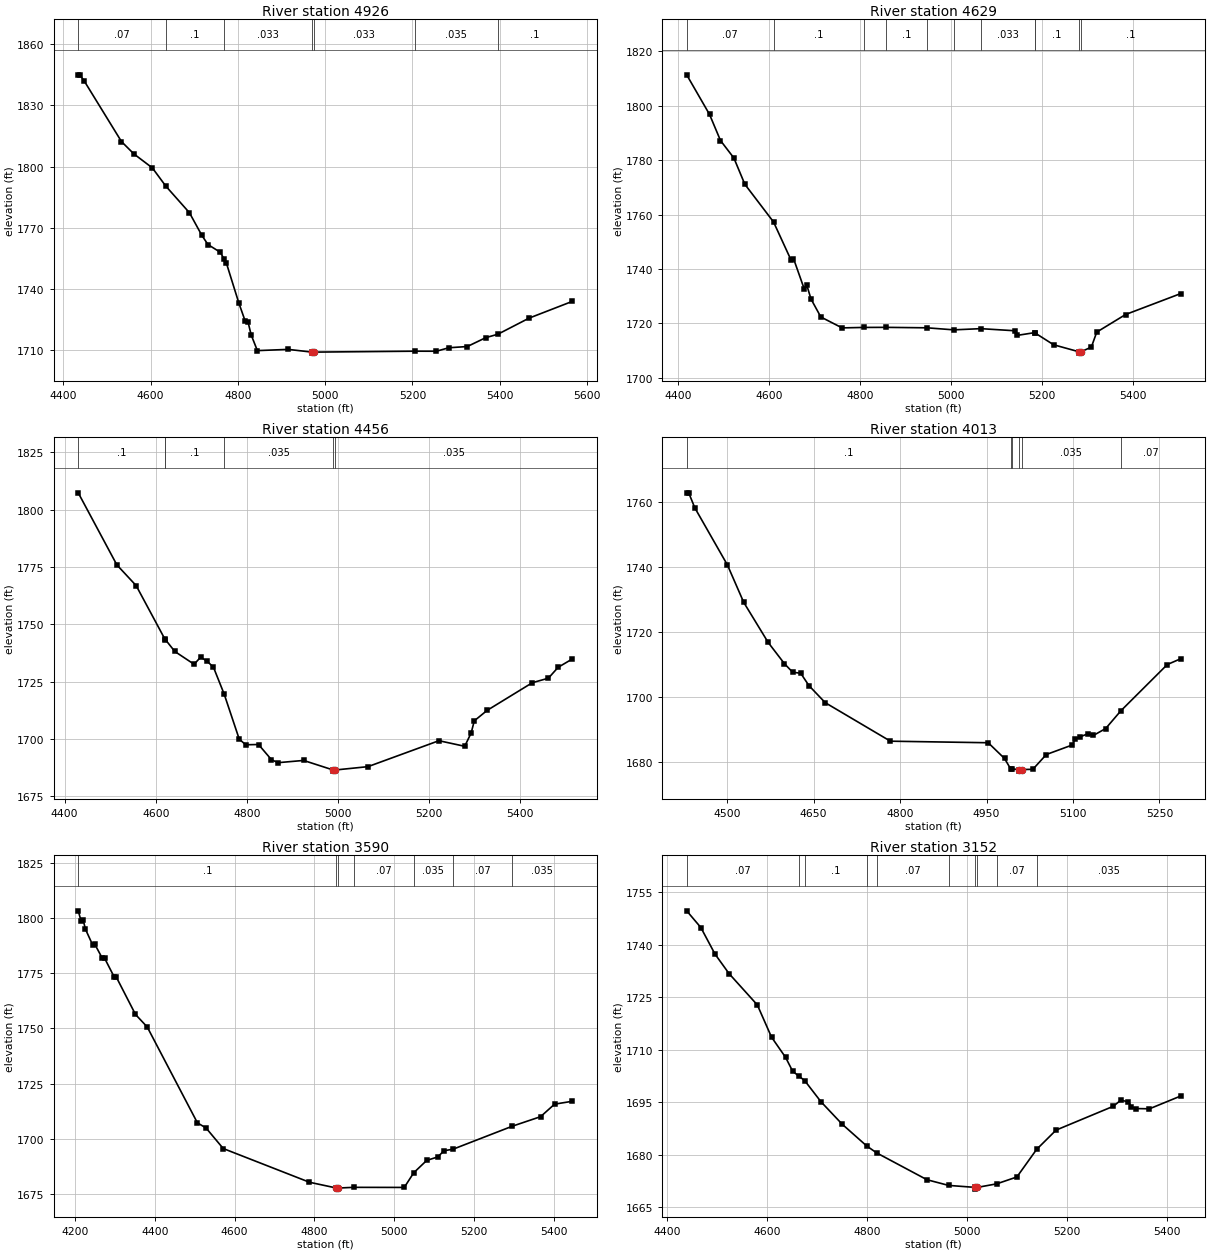
Type RM Length L Ch R = 1,4926,297,297,297
BEGIN DESCRIPTION:
Stream0076 11.0
END DESCRIPTION:
XS GIS Cut Line= 3
      1996875.02     13929924.98      1996475.00     13930325.00
      1996075.00     13930725.00
#Sta/Elev= 30
  4434.5 1845.01  4438.1 1845.01  4448.7 1841.82  4533.5 1812.31  4561.8 1806.28
  4604.2 1799.41  4634.9 1790.52  4689.1 1777.45  4717.4 1766.42  4731.5 1761.86
  4759.8 1758.07  4769.0 1754.56  4773.9 1752.69  4802.2 1733.26  4816.4 1724.60
  4823.4 1723.86  4830.5 1717.61  4844.7 1709.88  4915.4 1710.48  4969.6 1709.15
  4969.9 1708.65  4974.3 1709.15  5205.3 1709.60  5254.8 1709.58  5283.1 1711.28
  5325.5 1711.88  5367.9 1716.24  5395.4 1717.90  5466.9 1725.79  5565.9 1734.00
#Mann=7,-1,0
  4434.5    0.07       0  4634.9     0.1       0  4769.0   0.033       0
  4969.6   0.033       0  4974.3   0.033       0  5205.3   0.035       0
  5395.4     0.1       0
Bank Sta=4969.6,4974.3
Exp/Cntr=0.3,0.1

Type RM Length L Ch R = 1,4629,173,173,173
BEGIN DESCRIPTION:
Mapping XS 3af38242
END DESCRIPTION:
XS GIS Cut Line= 5
      1996748.04     13929921.61      1996359.62     13930080.01
      1996231.58     13930175.50      1996114.40     13930349.11
      1996020.42     13930631.31
#Sta/Elev= 30
  4418.5 1811.40  4468.8 1796.81  4492.8 1787.24  4522.3 1780.80  4546.3 1771.16
  4609.5 1757.27  4647.9 1743.29  4653.3 1743.85  4677.3 1732.48  4682.7 1733.95
  4691.8 1728.95  4713.4 1722.34  4760.2 1718.33  4807.3 1718.50  4857.0 1718.53
  4946.8 1718.36  5005.7 1717.61  5065.0 1718.05  5139.7 1717.28  5145.7 1715.59
  5183.2 1716.58  5183.4 1716.57  5225.1 1712.13  5280.8 1709.55  5281.1 1709.05
  5285.5 1709.55  5308.2 1711.29  5320.0 1716.78  5383.3 1723.24  5504.6 1730.95
#Mann=11,-1,0
  4418.5    0.07       0  4609.5     0.1       0  4807.3   0.033       0
  4857.0     0.1       0  4946.8   0.033       0  5005.7     0.1       0
  5065.0   0.033       0  5183.2   0.035       0  5183.4     0.1       0
  5280.8   0.033       0  5285.5     0.1       0
Bank Sta=5280.8,5285.5
Exp/Cntr=0.3,0.1

Type RM Length L Ch R = 1,4456,443,443,443
BEGIN DESCRIPTION:
Stream0076 10.0
END DESCRIPTION:
XS GIS Cut Line= 3
      1996574.97     13929625.03      1996175.00     13930025.00
      1995820.28     13930404.21
#Sta/Elev= 30
  4429.8 1807.35  4514.6 1775.92  4557.0 1766.87  4620.0 1743.57  4621.1 1743.34
  4641.9 1738.15  4684.3 1732.56  4698.5 1735.67  4712.6 1733.92  4726.7 1731.30
  4750.4 1719.48  4783.3 1699.94  4797.5 1697.46  4825.7 1697.57  4854.0 1690.98
  4868.2 1689.64  4924.7 1690.62  4989.6 1686.46  4989.9 1685.96  4994.3 1686.46
  5066.0 1687.91  5221.9 1699.23  5278.5 1696.79  5292.7 1702.63  5299.5 1707.89
  5327.9 1712.48  5427.0 1724.53  5462.2 1726.49  5483.7 1731.25  5514.7 1734.87
#Mann=6,-1,0
  4429.8     0.1       0  4620.0   0.035       0  4621.1     0.1       0
  4750.4   0.035       0  4989.6   0.035       0  4994.3   0.035       0
Bank Sta=4989.6,4994.3
Exp/Cntr=0.3,0.1

Type RM Length L Ch R = 1,4013,423,423,423
BEGIN DESCRIPTION:
Stream0076 9.0
END DESCRIPTION:
XS GIS Cut Line= 3
      1996224.97     13929375.03      1995825.00     13929775.00
      1995675.00     13930025.01
#Sta/Elev= 30
  4429.7 1762.83  4433.2 1762.83  4443.8 1758.21  4500.4 1740.61  4528.7 1729.09
  4571.1 1716.75  4599.4 1710.20  4613.5 1707.60  4627.6 1707.26  4641.8 1703.47
  4670.1 1698.21  4783.2 1686.35  4952.9 1685.87  4981.2 1681.02  4991.9 1677.80
  4994.1 1677.80  5006.6 1677.63  5006.9 1677.13  5011.4 1677.63  5030.3 1677.68
  5053.7 1682.24  5098.4 1685.16  5104.2 1687.05  5112.0 1687.69  5125.6 1688.60
  5135.3 1688.11  5156.7 1690.25  5182.9 1695.68  5263.6 1709.95  5286.9 1711.74
#Mann=6,-1,0
  4429.7     0.1       0  4991.9    0.07       0  4994.1   0.035       0
  5006.6   0.035       0  5011.4   0.035       0  5182.9    0.07       0
Bank Sta=5006.6,5011.4
Exp/Cntr=0.3,0.1

Type RM Length L Ch R = 1,3590,438,438,438
BEGIN DESCRIPTION:
Stream0076 8.0
END DESCRIPTION:
XS GIS Cut Line= 3
      1996311.48     13929175.44      1995575.00     13929475.00
      1995233.77     13929756.46
#Sta/Elev= 30
  4208.5 1803.43  4215.3 1799.00  4220.7 1799.46  4226.3 1795.19  4244.8 1787.85
  4250.2 1788.17  4268.9 1781.86  4274.3 1781.99  4298.3 1773.49  4303.7 1773.39
  4351.9 1756.37  4381.3 1750.68  4507.0 1707.15  4528.6 1704.82  4571.7 1695.48
  4787.7 1680.17  4855.3 1677.55  4855.7 1677.05  4860.2 1677.55  4898.1 1677.86
  5025.1 1677.82  5048.8 1684.48  5081.3 1690.09  5109.7 1691.71  5124.1 1694.47
  5147.2 1695.18  5296.1 1705.65  5366.5 1709.95  5401.6 1715.64  5445.9 1716.94
#Mann=7,-1,0
  4208.5     0.1       0  4855.3    0.05       0  4860.2     0.1       0
  4898.1    0.07       0  5048.8   0.035       0  5147.2    0.07       0
  5296.1   0.035       0
Bank Sta=4855.3,4860.2
Exp/Cntr=0.3,0.1

Type RM Length L Ch R = 1,3152,372,372,372
BEGIN DESCRIPTION:
Stream0076 7.0
END DESCRIPTION:
XS GIS Cut Line= 3
      1995824.99     13928725.01      1995425.00     13929125.00
      1995193.48     13929478.81
#Sta/Elev= 30
  4439.1 1749.64  4467.4 1744.88  4495.7 1737.31  4523.9 1731.72  4580.5 1722.78
  4608.8 1713.61  4637.1 1707.80  4651.2 1703.85  4664.2 1702.41  4675.3 1701.18
  4707.8 1695.16  4750.2 1688.76  4799.1 1682.57  4819.2 1680.57  4919.9 1672.91
  4963.2 1671.29  5015.9 1670.73  5016.2 1670.23  5020.8 1670.73  5059.5 1671.74
  5099.8 1673.70  5139.3 1681.57  5178.2 1687.07  5292.7 1693.87  5307.8 1695.62
  5322.9 1695.13  5328.9 1693.70  5338.0 1693.22  5365.1 1693.15  5427.6 1696.80
#Mann=10,-1,0
  4439.1    0.07       0  4664.2   0.035       0  4675.3     0.1       0
  4799.1   0.035       0  4819.2    0.07       0  4963.2   0.035       0
  5015.9   0.035       0  5020.8   0.035       0  5059.5    0.07       0
  5139.3   0.035       0
Bank Sta=5015.9,5020.8
Exp/Cntr=0.3,0.1

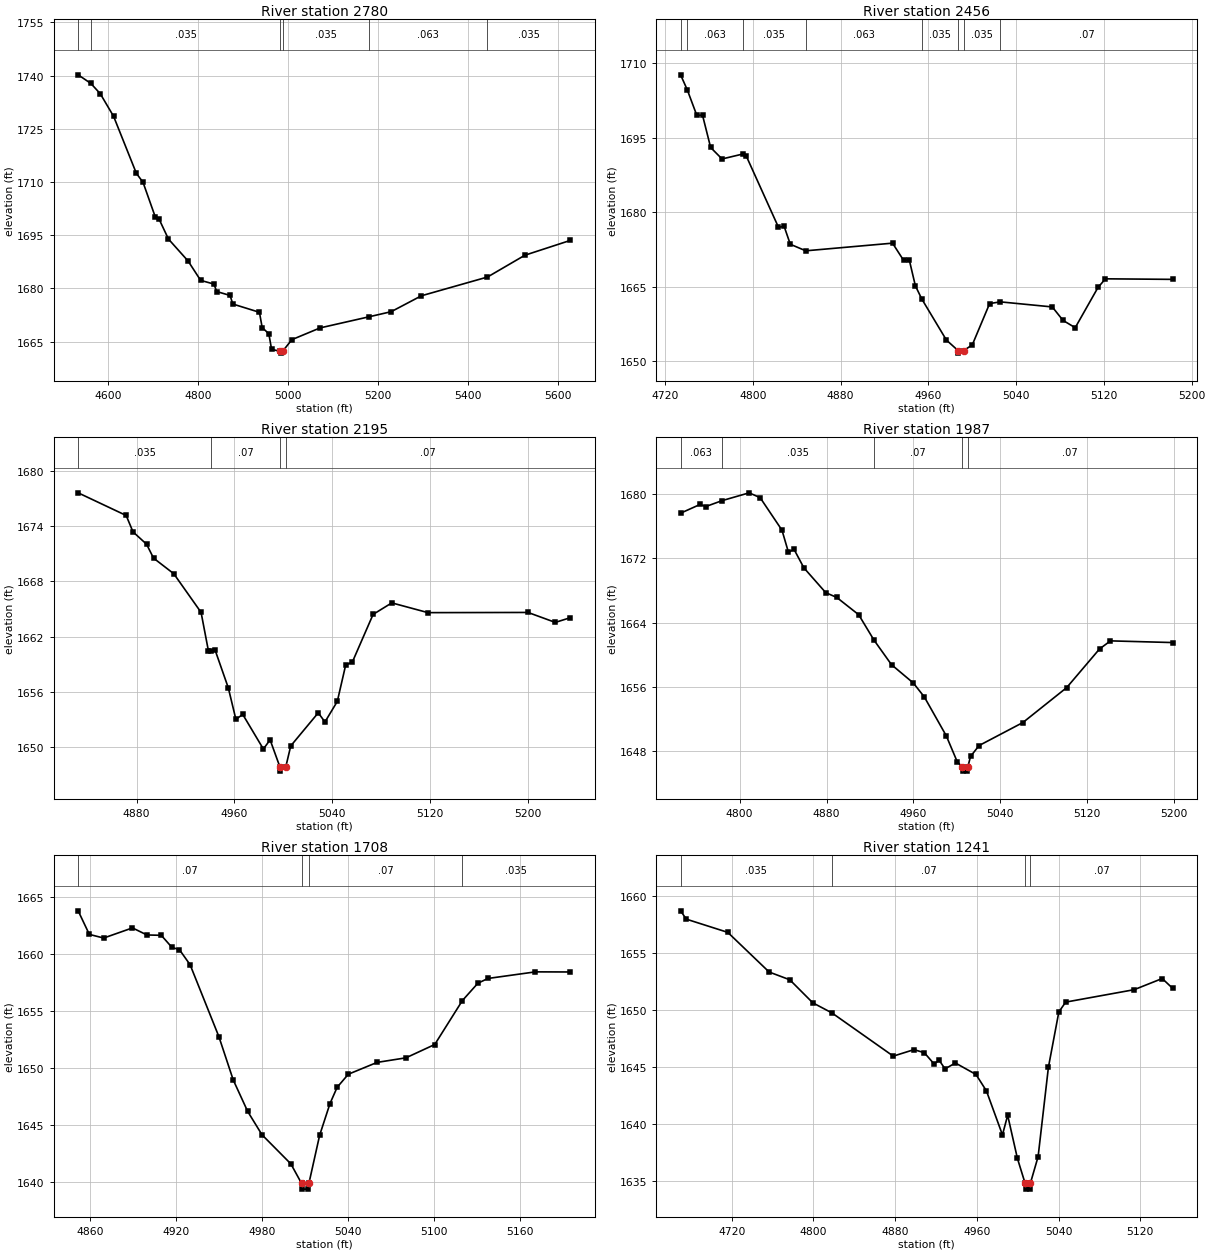
Type RM Length L Ch R = 1,2780,324,324,324
BEGIN DESCRIPTION:
Stream0076 6.0
END DESCRIPTION:
XS GIS Cut Line= 3
      1995524.98     13928425.02      1995255.85     13928808.40
      1995201.31     13929431.70
#Sta/Elev= 30
  4533.5 1740.22  4561.6 1737.81  4582.7 1734.89  4612.3 1728.52  4662.9 1712.46
  4677.7 1709.93  4704.7 1700.26  4713.4 1699.55  4734.3 1693.92  4777.8 1687.76
  4805.8 1682.29  4835.4 1681.24  4841.5 1679.14  4871.2 1678.04  4877.3 1675.62
  4936.5 1673.29  4942.6 1669.00  4957.4 1667.23  4963.5 1662.85  4983.0 1662.28
  4983.4 1661.78  4988.0 1662.28  5008.5 1665.57  5071.4 1668.89  5179.7 1672.01
  5229.4 1673.46  5296.5 1677.94  5443.5 1683.23  5526.7 1689.38  5627.6 1693.55
#Mann=6,-1,0
  4533.5    0.07       0  4561.6   0.035       0  4983.0   0.035       0
  4988.0   0.035       0  5179.7   0.063       0  5443.5   0.035       0
Bank Sta=4983,4988
Exp/Cntr=0.3,0.1

Type RM Length L Ch R = 1,2456,261,261,261
BEGIN DESCRIPTION:
Mapping XS 1dd02800
END DESCRIPTION:
XS GIS Cut Line= 3
      1995381.46     13928465.34      1995145.37     13928529.57
      1994949.62     13928586.73
#Sta/Elev= 30
  4734.1 1707.65  4740.2 1704.63  4748.9 1699.48  4754.1 1699.52  4761.5 1693.02
  4771.9 1690.71  4790.7 1691.70  4793.9 1691.34  4823.3 1676.97  4828.5 1677.13
  4834.1 1673.54  4848.2 1672.22  4927.3 1673.76  4937.4 1670.29  4942.6 1670.34
  4948.1 1665.18  4954.0 1662.50  4976.4 1654.25  4987.1 1652.12  4987.4 1651.62
  4992.1 1652.12  5000.0 1653.29  5015.8 1661.60  5025.6 1661.94  5072.9 1660.92
  5082.7 1658.21  5093.8 1656.74  5114.6 1664.85  5121.4 1666.58  5182.7 1666.47
#Mann=8,-1,0
  4734.1   0.035       0  4740.2   0.063       0  4790.7   0.035       0
  4848.2   0.063       0  4954.0   0.035       0  4987.1   0.035       0
  4992.1   0.035       0  5025.6    0.07       0
Bank Sta=4987.1,4992.1
Exp/Cntr=0.3,0.1

Type RM Length L Ch R = 1,2195,208,208,208
BEGIN DESCRIPTION:
Mapping XS c7d4e60b
END DESCRIPTION:
XS GIS Cut Line= 2
      1995225.27     13928232.67      1994863.97     13928410.73
#Sta/Elev= 30
  4832.1 1677.62  4871.4 1675.16  4877.0 1673.38  4888.1 1672.04  4893.8 1670.53
  4910.4 1668.83  4932.7 1664.64  4938.7 1660.47  4940.8 1660.48  4944.3 1660.50
  4955.0 1656.44  4961.2 1653.02  4966.8 1653.56  4983.7 1649.80  4989.2 1650.80
  4997.1 1647.90  4997.5 1647.40  5002.1 1647.90  5006.1 1650.14  5028.6 1653.73
  5034.1 1652.74  5044.2 1654.97  5051.0 1658.89  5056.6 1659.27  5073.5 1664.42
  5088.8 1665.67  5118.4 1664.61  5200.3 1664.63  5222.6 1663.55  5234.9 1664.06
#Mann=4,-1,0
  4832.1   0.035       0  4940.8    0.07       0  4997.1    0.05       0
  5002.1    0.07       0
Bank Sta=4997.1,5002.1
Exp/Cntr=0.3,0.1

Type RM Length L Ch R = 1,1987,279,279,279
BEGIN DESCRIPTION:
Mapping XS 2c0828fd
END DESCRIPTION:
XS GIS Cut Line= 2
      1995327.63     13928067.77      1994878.13     13928123.09
#Sta/Elev= 30
  4745.7 1677.59  4763.7 1678.68  4768.8 1678.41  4783.9 1679.15  4808.8 1680.12
  4818.9 1679.52  4839.0 1675.48  4845.0 1672.71  4850.0 1673.12  4859.2 1670.79
  4879.3 1667.71  4889.4 1667.12  4909.6 1664.97  4923.7 1661.81  4939.8 1658.76
  4959.9 1656.48  4970.0 1654.75  4990.2 1649.92  5000.2 1646.72  5004.9 1646.03
  5005.3 1645.53  5009.6 1645.53  5010.0 1646.03  5012.5 1647.35  5020.4 1648.71
  5060.7 1651.57  5101.0 1655.91  5131.2 1660.71  5141.3 1661.72  5198.6 1661.51
#Mann=5,-1,0
  4745.7   0.063       0  4783.9   0.035       0  4923.7    0.07       0
  5004.9    0.05       0  5010.0    0.07       0
Bank Sta=5004.9,5010
Exp/Cntr=0.3,0.1

Type RM Length L Ch R = 1,1708,467,467,467
BEGIN DESCRIPTION:
Mapping XS b5c36abe
END DESCRIPTION:
XS GIS Cut Line= 2
      1995122.76     13927843.81      1994780.79     13927875.05
#Sta/Elev= 30
  4851.6 1663.82  4859.4 1661.75  4869.4 1661.43  4889.5 1662.32  4899.6 1661.70
  4909.6 1661.67  4917.1 1660.60  4922.2 1660.42  4929.7 1659.09  4949.8 1652.77
  4959.8 1648.97  4969.9 1646.20  4979.9 1644.15  5000.0 1641.60  5007.5 1639.88
  5007.9 1639.38  5012.2 1639.38  5012.6 1639.88  5020.1 1644.11  5027.3 1646.89
  5032.3 1648.32  5040.1 1649.47  5060.2 1650.51  5080.3 1650.91  5100.4 1652.08
  5119.7 1655.94  5130.5 1657.46  5137.5 1657.88  5170.7 1658.46  5195.0 1658.45
#Mann=4,-1,0
  4851.6    0.07       0  5007.5    0.05       0  5012.6    0.07       0
  5119.7   0.035       0
Bank Sta=5007.5,5012.6
Exp/Cntr=0.3,0.1

Type RM Length L Ch R = 1,1241,195,195,195
BEGIN DESCRIPTION:
Mapping XS 71e16817
END DESCRIPTION:
XS GIS Cut Line= 2
      1995150.58     13927500.05      1994674.87     13927423.66
#Sta/Elev= 30
  4670.0 1658.72  4675.6 1657.99  4716.2 1656.83  4756.7 1653.35  4776.9 1652.67
  4799.4 1650.65  4818.2 1649.76  4878.2 1645.97  4898.5 1646.54  4908.6 1646.27
  4918.1 1645.29  4923.2 1645.60  4928.9 1644.85  4939.0 1645.37  4959.2 1644.36
  4969.4 1642.92  4985.1 1639.06  4990.2 1640.78  4999.7 1637.01  5007.3 1634.80
  5007.7 1634.30  5012.0 1634.30  5012.4 1634.80  5020.0 1637.15  5030.1 1645.00
  5040.3 1649.85  5047.0 1650.71  5114.0 1651.80  5141.5 1652.78  5151.8 1651.91
#Mann=4,-1,0
  4670.0   0.035       0  4818.2    0.07       0  5007.3    0.05       0
  5012.4    0.07       0
Bank Sta=5007.3,5012.4
Exp/Cntr=0.3,0.1

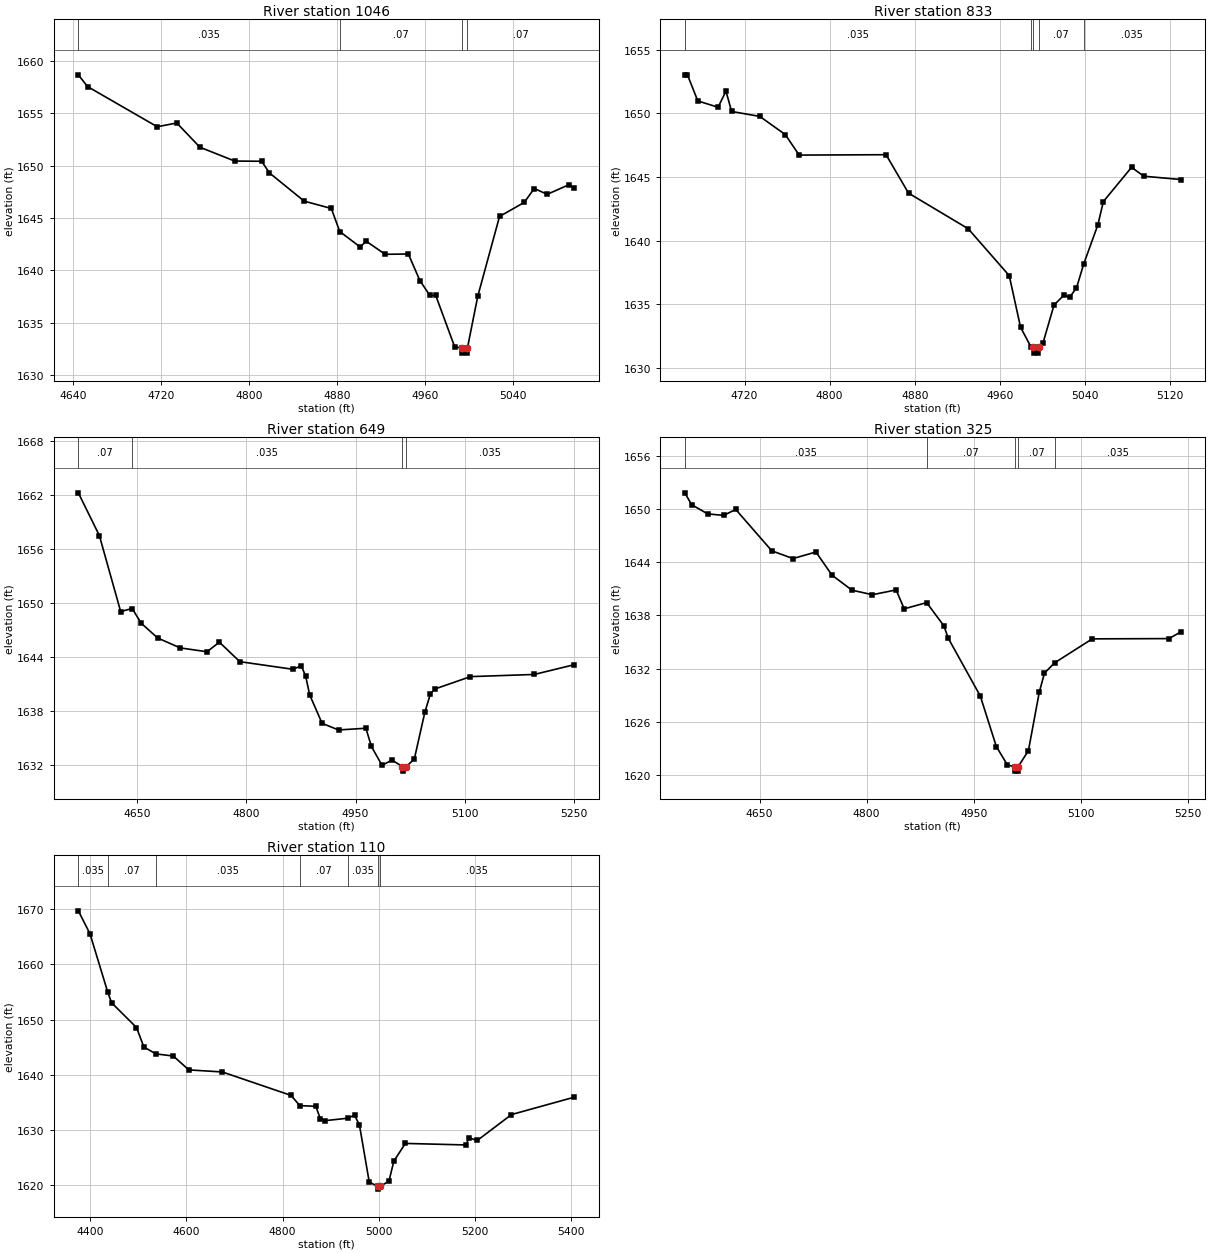
Type RM Length L Ch R = 1,1046,213,213,213
BEGIN DESCRIPTION:
Mapping XS 1760eda0
END DESCRIPTION:
XS GIS Cut Line= 2
      1995220.01     13927381.99      1994791.79     13927239.83
#Sta/Elev= 30
  4644.7 1658.65  4653.1 1657.53  4716.5 1653.70  4734.3 1654.06  4755.3 1651.75
  4787.0 1650.43  4811.5 1650.41  4818.6 1649.30  4850.2 1646.61  4874.9 1645.91
  4882.6 1643.71  4901.3 1642.23  4906.5 1642.80  4923.9 1641.54  4945.0 1641.57
  4955.5 1639.04  4964.6 1637.62  4969.9 1637.63  4987.2 1632.71  4993.7 1632.62
  4994.1 1632.12  4998.4 1632.12  4998.8 1632.62  5008.2 1637.55  5028.0 1645.15
  5050.4 1646.48  5059.6 1647.81  5071.4 1647.26  5091.3 1648.18  5095.9 1647.84
#Mann=4,-1,0
  4644.7   0.035       0  4882.6    0.07       0  4993.7    0.05       0
  4998.8    0.07       0
Bank Sta=4993.7,4998.8
Exp/Cntr=0.3,0.1

Type RM Length L Ch R = 1,833,184,184,184
BEGIN DESCRIPTION:
Mapping XS 10ea1908
END DESCRIPTION:
XS GIS Cut Line= 2
      1995294.71     13927192.77      1994852.01     13927046.94
#Sta/Elev= 30
  4663.8 1653.04  4666.3 1653.04  4676.0 1650.99  4695.1 1650.49  4702.5 1651.76
  4707.8 1650.16  4734.3 1649.77  4758.3 1648.34  4771.3 1646.73  4853.0 1646.76
  4874.1 1643.74  4930.2 1640.94  4968.8 1637.25  4979.4 1633.20  4989.0 1631.68
  4991.2 1631.66  4991.6 1631.16  4995.9 1631.16  4996.3 1631.66  5000.4 1631.92
  5010.9 1634.94  5020.2 1635.72  5025.5 1635.55  5032.0 1636.28  5038.8 1638.17
  5052.0 1641.22  5057.3 1643.08  5083.8 1645.77  5095.2 1645.07  5129.9 1644.81
#Mann=5,-1,0
  4663.8   0.035       0  4989.0    0.07       0  4991.2    0.05       0
  4996.3    0.07       0  5038.8   0.035       0
Bank Sta=4991.2,4996.3
Exp/Cntr=0.3,0.1

Type RM Length L Ch R = 1,649,324,324,324
BEGIN DESCRIPTION:
Mapping XS 5725be1b
END DESCRIPTION:
XS GIS Cut Line= 3
      1995411.01     13927105.96      1994968.29     13926892.42
      1994780.81     13926923.66
#Sta/Elev= 30
  4568.9 1662.24  4597.8 1657.50  4627.1 1649.06  4642.9 1649.40  4655.3 1647.77
  4677.9 1646.13  4708.8 1645.03  4745.7 1644.60  4762.8 1645.66  4790.9 1643.50
  4864.3 1642.65  4875.3 1643.06  4881.4 1641.89  4886.9 1639.82  4904.0 1636.65
  4926.6 1635.92  4964.2 1636.11  4971.8 1634.09  4986.4 1631.99  5000.0 1632.58
  5014.5 1631.85  5014.9 1631.35  5019.6 1631.85  5030.8 1632.70  5045.2 1637.87
  5053.0 1639.95  5059.5 1640.48  5108.0 1641.84  5195.6 1642.08  5250.5 1643.16
#Mann=4,-1,0
  4568.9    0.07       0  4642.9   0.035       0  5014.5   0.035       0
  5019.6   0.035       0
Bank Sta=5014.5,5019.6
Exp/Cntr=0.3,0.1

Type RM Length L Ch R = 1,325,215,215,215
BEGIN DESCRIPTION:
Mapping XS 739bb691
END DESCRIPTION:
XS GIS Cut Line= 3
      1995581.16     13926862.91      1995117.60     13926635.47
      1994939.42     13926651.04
#Sta/Elev= 30
  4545.0 1651.81  4554.5 1650.48  4577.0 1649.44  4599.5 1649.27  4616.4 1649.94
  4667.0 1645.28  4696.7 1644.41  4728.9 1645.15  4751.4 1642.54  4779.4 1640.85
  4808.0 1640.34  4841.3 1640.88  4852.6 1638.75  4884.1 1639.45  4908.3 1636.83
  4914.4 1635.44  4959.3 1628.94  4981.8 1623.25  4997.4 1621.17  5007.3 1620.98
  5007.7 1620.48  5012.1 1620.48  5012.4 1620.98  5026.8 1622.79  5042.0 1629.36
  5049.3 1631.52  5063.5 1632.67  5116.3 1635.37  5223.9 1635.40  5240.2 1636.14
#Mann=5,-1,0
  4545.0   0.035       0  4884.1    0.07       0  5007.3    0.05       0
  5012.4    0.07       0  5063.5   0.035       0
Bank Sta=5007.3,5012.4
Exp/Cntr=0.3,0.1

Type RM Length L Ch R = 1,110,0,0,0
BEGIN DESCRIPTION:
Stream0076 0.0
END DESCRIPTION:
XS GIS Cut Line= 4
      1995888.82     13926602.91      1995259.52     13926481.39
      1995085.91     13926522.62      1994914.45     13926646.34
#Sta/Elev= 30
  4375.4 1669.68  4399.7 1665.51  4436.7 1654.92  4444.5 1653.05  4496.3 1648.57
  4511.7 1645.04  4536.5 1643.80  4572.8 1643.41  4605.1 1640.90  4674.6 1640.53
  4817.5 1636.29  4835.9 1634.44  4869.3 1634.31  4878.3 1632.08  4888.5 1631.72
  4935.7 1632.16  4949.6 1632.72  4959.8 1630.94  4980.2 1620.60  4998.0 1619.83
  4998.4 1619.33  5003.2 1619.83  5021.2 1620.79  5031.3 1624.39  5055.3 1627.60
  5181.8 1627.32  5187.0 1628.63  5204.7 1628.13  5275.9 1632.82  5406.2 1635.96
#Mann=7,-1,0
  4375.4   0.035       0  4436.7    0.07       0  4536.5   0.035       0
  4835.9    0.07       0  4935.7   0.035       0  4998.0   0.035       0
  5003.2   0.035       0
Bank Sta=4998,5003.2
Exp/Cntr=0.3,0.1

Chan Stop Cuts=-1