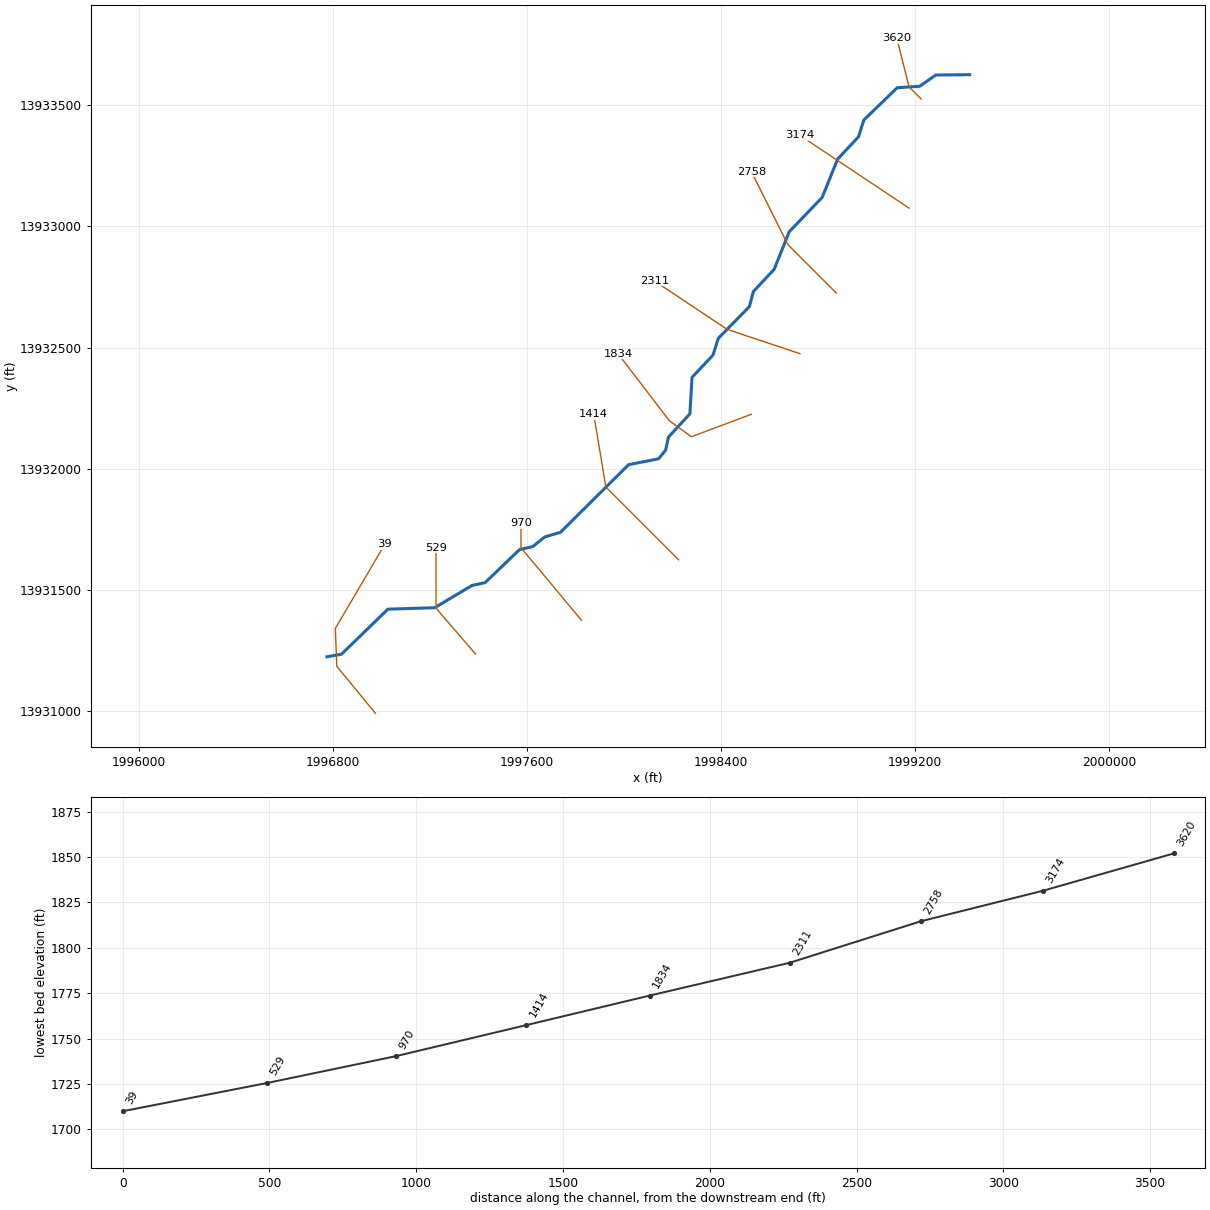
--- Stream0077.prj (project) ---

Proj Title=Stream0077 Base Level Engineering
Current Plan=p01
Default Exp/Contr=0.3,0.1
English Units
Geom File=g01
Flow File=f01
Plan File=p01
BEGIN DESCRIPTION:
Stream0077
END DESCRIPTION:

--- Stream0077.p01 (plan) ---

Plan Title=Multiple Run
Short Identifier=Multiple
Geom File=g01
Flow File=f01
Subcritical Flow
K Sum by GR= 0
Std Step Tol= 0.01
Critical Tol= 0.01
Num of Std Step Trials= 20
Max Error Tol= 0.3
Flow Tol Ratio= 0.001
Split Flow NTrial= 30
Split Flow Tol= 0.02
Split Flow Ratio= 0.02
Log Output Level= 0
Friction Slope Method= 1
Unsteady Friction Slope Method= 2
Unsteady Bridges Friction Slope Method= 1
Parabolic Critical Depth
Global Vel Dist=  1 , 1 , 1
Global Log Level= 0
CheckData=True
Encroach Param= -1, 0, 0, 0
BEGIN DESCRIPTION:
Multiple Run
END DESCRIPTION:

--- Stream0077.f01 (steady flow) ---

Flow Title=Multiple
Number of Profiles=7
Profile Names=10-year,25-year,50-year,1pct_min,100-year,1pct_plu,500-year
River Rch & RM= Stream0077,Reach-1,3620
     439     720     981     651    1299    2592    2253
Boundary for River Rch & Prof#=Stream0077,Reach-1,1
Up Type=0
Dn Type=3
Dn Slope=0.005
Boundary for River Rch & Prof#=Stream0077,Reach-1,2
Up Type=0
Dn Type=3
Dn Slope=0.005
Boundary for River Rch & Prof#=Stream0077,Reach-1,3
Up Type=0
Dn Type=3
Dn Slope=0.005
Boundary for River Rch & Prof#=Stream0077,Reach-1,4
Up Type=0
Dn Type=3
Dn Slope=0.005
Boundary for River Rch & Prof#=Stream0077,Reach-1,5
Up Type=0
Dn Type=3
Dn Slope=0.005
Boundary for River Rch & Prof#=Stream0077,Reach-1,6
Up Type=0
Dn Type=3
Dn Slope=0.005
Boundary for River Rch & Prof#=Stream0077,Reach-1,7
Up Type=0
Dn Type=3
Dn Slope=0.005

--- Stream0077.g01 (geometry) ---

Geom Title=Existing Conditions

River Reach=Stream0077,Reach-1
Reach XY= 30
      1999425.00     13933625.00      1999285.48     13933623.83
      1999219.02     13933577.36      1999126.50     13933571.39
      1998988.63     13933438.21      1998966.82     13933368.96
      1998880.85     13933277.29      1998816.86     13933118.94
      1998680.83     13932977.30      1998619.15     13932822.71
      1998533.18     13932731.04      1998516.84     13932668.95
      1998388.63     13932538.21      1998366.82     13932468.96
      1998280.48     13932377.44      1998271.45     13932226.47
      1998183.19     13932131.02      1998171.13     13932076.40
      1998142.13     13932041.30      1998018.83     13932017.14
      1997738.21     13931738.62      1997672.81     13931718.90
      1997623.26     13931679.19      1997568.94     13931666.86
      1997427.30     13931530.83      1997372.81     13931518.90
      1997219.07     13931427.24      1997026.46     13931421.46
      1996834.79     13931235.52      1996775.00     13931225.00

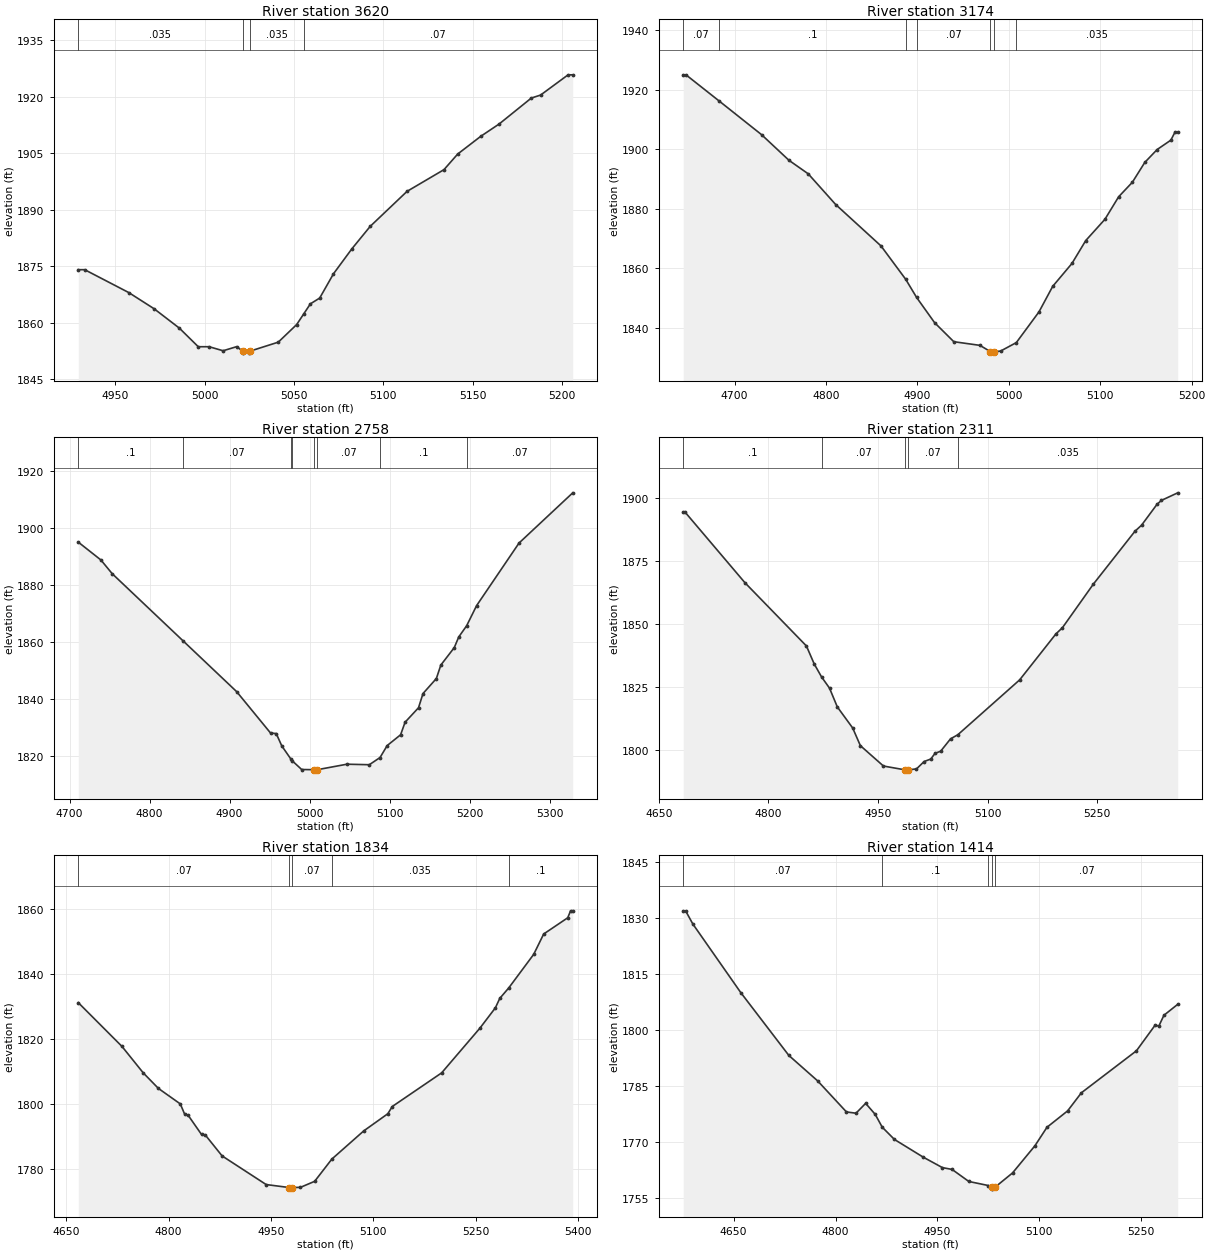
Type RM Length L Ch R = 1,3620,446,446,446
BEGIN DESCRIPTION:
Stream0077 8.0
END DESCRIPTION:
XS GIS Cut Line= 3
      1999225.03     13933524.97      1999175.00     13933575.00
      1999125.00     13933774.99
#Sta/Elev= 30
  4929.2 1874.09  4932.8 1874.09  4957.5 1868.01  4971.7 1863.71  4985.8 1858.58
  4996.4 1853.64  5002.5 1853.64  5010.3 1852.57  5018.0 1853.67  5021.2 1852.44
  5021.4 1851.94  5024.9 1851.94  5025.2 1852.44  5041.2 1854.85  5051.5 1859.52
  5055.5 1862.38  5059.2 1865.03  5064.4 1866.56  5072.1 1872.99  5082.4 1879.62
  5092.7 1885.60  5113.3 1894.88  5134.0 1900.65  5141.7 1904.80  5154.6 1909.50
  5164.9 1912.77  5182.9 1919.65  5188.1 1920.45  5203.5 1925.82  5206.1 1925.82
#Mann=4,-1,0
  4929.2   0.035       0  5021.2   0.035       0  5025.2   0.035       0
  5055.5    0.07       0
Bank Sta=5021.2,5025.2
Exp/Cntr=0.3,0.1

Type RM Length L Ch R = 1,3174,416,416,416
BEGIN DESCRIPTION:
Stream0077 7.0
END DESCRIPTION:
XS GIS Cut Line= 3
      1999174.98     13933075.01      1998875.00     13933275.00
      1998725.01     13933374.99
#Sta/Elev= 30
  4643.9 1924.94  4646.9 1924.94  4683.1 1916.16  4729.5 1904.84  4759.6 1896.19
  4780.6 1891.66  4810.6 1881.35  4860.2 1867.42  4887.2 1856.21  4899.1 1850.12
  4918.8 1841.63  4939.8 1835.23  4968.4 1834.00  4979.9 1831.89  4980.1 1831.39
  4983.9 1831.89  4990.9 1832.07  5008.2 1834.93  5033.0 1845.27  5048.0 1853.85
  5069.0 1861.52  5084.1 1869.22  5105.1 1876.38  5120.1 1883.95  5135.1 1888.83
  5148.7 1895.50  5162.2 1899.83  5177.2 1902.98  5181.7 1905.67  5184.7 1905.67
#Mann=7,-1,0
  4643.9    0.07       0  4683.1     0.1       0  4887.2   0.035       0
  4899.1    0.07       0  4979.9    0.05       0  4983.9    0.07       0
  5008.2   0.035       0
Bank Sta=4979.9,4983.9
Exp/Cntr=0.3,0.1

Type RM Length L Ch R = 1,2758,447,447,447
BEGIN DESCRIPTION:
Stream0077 6.0
END DESCRIPTION:
XS GIS Cut Line= 3
      1998874.98     13932725.02      1998675.00     13932925.00
      1998525.01     13933224.98
#Sta/Elev= 30
  4710.8 1895.01  4739.1 1888.74  4753.2 1883.93  4841.6 1860.40  4908.8 1842.51
  4951.2 1827.97  4958.3 1827.78  4965.3 1823.42  4976.5 1818.88  4977.9 1818.32
  4990.1 1815.16  5005.6 1815.09  5005.8 1814.59  5009.6 1815.09  5046.7 1817.02
  5074.7 1816.84  5088.1 1819.37  5097.0 1823.56  5113.8 1827.36  5119.4 1831.77
  5136.2 1836.85  5141.8 1841.84  5158.5 1847.11  5164.1 1851.84  5180.9 1857.97
  5186.5 1861.71  5196.4 1865.66  5208.8 1872.71  5261.9 1894.70  5329.0 1912.32
#Mann=8,-1,0
  4710.8     0.1       0  4841.6    0.07       0  4976.5   0.035       0
  4977.9    0.07       0  5005.6    0.05       0  5009.6    0.07       0
  5088.1     0.1       0  5196.4    0.07       0
Bank Sta=5005.6,5009.6
Exp/Cntr=0.3,0.1

Type RM Length L Ch R = 1,2311,477,477,477
BEGIN DESCRIPTION:
Stream0077 5.0
END DESCRIPTION:
XS GIS Cut Line= 3
      1998724.96     13932475.01      1998425.00     13932575.00
      1998125.04     13932774.98
#Sta/Elev= 30
  4683.6 1894.55  4686.2 1894.55  4767.9 1866.60  4852.2 1841.43  4862.8 1834.32
  4872.9 1829.14  4883.8 1824.68  4894.4 1817.26  4915.5 1808.86  4926.0 1801.86
  4957.6 1793.76  4987.2 1792.24  4987.5 1791.74  4991.2 1792.24  5002.8 1792.62
  5013.3 1795.56  5022.3 1796.53  5028.3 1798.84  5035.8 1799.62  5049.4 1804.56
  5059.4 1806.19  5144.0 1827.98  5193.6 1846.22  5202.6 1848.72  5244.7 1865.94
  5301.8 1887.00  5310.8 1889.39  5331.8 1897.62  5337.8 1899.21  5360.3 1902.25
#Mann=5,-1,0
  4683.6     0.1       0  4872.9    0.07       0  4987.2    0.05       0
  4991.2    0.07       0  5059.4   0.035       0
Bank Sta=4987.2,4991.2
Exp/Cntr=0.3,0.1

Type RM Length L Ch R = 1,1834,420,420,420
BEGIN DESCRIPTION:
Stream0077 4.0
END DESCRIPTION:
XS GIS Cut Line= 4
      1998525.04     13932225.02      1998277.83     13932132.26
      1998187.36     13932197.73      1997974.98     13932475.03
#Sta/Elev= 30
  4667.5 1831.24  4731.6 1817.72  4762.8 1809.55  4785.0 1804.76  4817.1 1799.98
  4823.3 1796.90  4828.6 1796.47  4848.2 1790.55  4853.5 1790.46  4878.4 1783.93
  4943.0 1775.09  4976.5 1774.18  4976.8 1773.68  4980.5 1774.18  4993.2 1774.22
  5014.1 1776.09  5039.3 1782.95  5086.0 1791.64  5121.4 1796.95  5127.9 1799.18
  5200.3 1809.56  5256.4 1823.36  5279.1 1829.64  5285.5 1832.54  5298.8 1835.81
  5335.3 1846.15  5349.9 1852.42  5385.2 1857.43  5389.3 1859.57  5392.5 1859.57
#Mann=5,-1,0
  4667.5    0.07       0  4976.5    0.05       0  4980.5    0.07       0
  5039.3   0.035       0  5298.8     0.1       0
Bank Sta=4976.5,4980.5
Exp/Cntr=0.3,0.1

Type RM Length L Ch R = 1,1414,444,444,444
BEGIN DESCRIPTION:
Stream0077 3.0
END DESCRIPTION:
XS GIS Cut Line= 3
      1998224.99     13931625.01      1997925.00     13931925.00
      1997875.00     13932225.01
#Sta/Elev= 30
  4575.7 1832.00  4579.2 1832.00  4589.8 1828.48  4660.5 1810.08  4731.3 1793.25
  4773.7 1786.44  4816.1 1778.12  4830.2 1777.78  4844.4 1780.42  4858.5 1777.47
  4868.8 1774.04  4886.8 1770.75  4929.2 1766.01  4957.5 1763.20  4971.7 1762.72
  4996.4 1759.49  5025.2 1758.40  5030.9 1757.94  5031.2 1757.44  5034.9 1757.94
  5060.8 1761.78  5093.7 1769.04  5111.5 1774.01  5141.9 1778.40  5162.2 1783.25
  5243.3 1794.50  5271.1 1801.44  5276.2 1801.09  5283.8 1804.02  5304.1 1806.95
#Mann=5,-1,0
  4575.7    0.07       0  4868.8     0.1       0  5025.2    0.07       0
  5030.9    0.05       0  5034.9    0.07       0
Bank Sta=5030.9,5034.9
Exp/Cntr=0.3,0.1

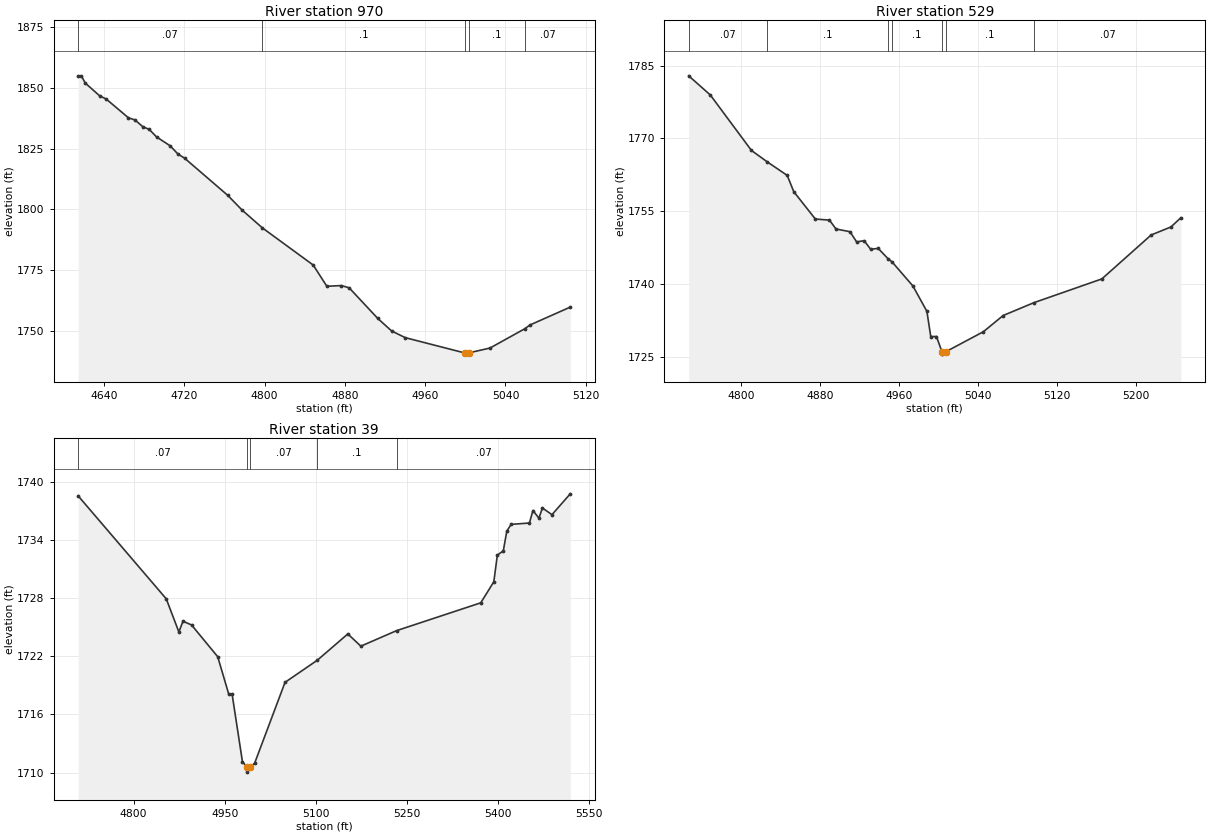
Type RM Length L Ch R = 1,970,441,441,441
BEGIN DESCRIPTION:
Stream0077 2.0
END DESCRIPTION:
XS GIS Cut Line= 3
      1997824.98     13931375.02      1997575.00     13931675.00
      1997575.00     13931775.02
#Sta/Elev= 30
  4614.1 1855.02  4617.3 1855.02  4621.2 1852.03  4635.5 1846.79  4642.1 1845.44
  4664.2 1837.73  4670.7 1836.86  4678.5 1834.08  4685.0 1832.93  4692.2 1829.87
  4705.8 1826.19  4713.6 1822.79  4720.2 1821.09  4763.1 1805.82  4777.4 1799.75
  4797.7 1792.38  4848.4 1777.06  4862.0 1768.31  4876.4 1768.61  4884.2 1767.69
  4912.8 1755.04  4926.5 1749.92  4940.1 1747.15  4999.3 1740.86  4999.6 1740.36
  5003.3 1740.86  5024.6 1742.87  5059.2 1750.80  5064.6 1752.40  5104.6 1759.73
#Mann=5,-1,0
  4614.1    0.07       0  4797.7     0.1       0  4999.3    0.05       0
  5003.3     0.1       0  5059.2    0.07       0
Bank Sta=4999.3,5003.3
Exp/Cntr=0.3,0.1

Type RM Length L Ch R = 1,529,490,490,490
BEGIN DESCRIPTION:
Stream0077 1.0
END DESCRIPTION:
XS GIS Cut Line= 3
      1997387.31     13931236.87      1997225.00     13931425.00
      1997225.00     13931675.03
#Sta/Elev= 30
  4747.0 1782.92  4768.9 1778.97  4810.6 1767.52  4826.4 1765.20  4846.8 1762.38
  4853.4 1759.04  4875.3 1753.38  4889.6 1753.16  4896.2 1751.33  4910.4 1750.77
  4917.1 1748.67  4924.7 1748.92  4931.3 1747.16  4939.0 1747.32  4949.1 1745.16
  4952.8 1744.59  4974.1 1739.58  4988.3 1734.34  4992.2 1729.15  4998.0 1729.15
  5003.5 1726.02  5003.7 1725.52  5007.5 1726.02  5045.5 1730.14  5065.5 1733.48
  5096.9 1736.15  5165.5 1741.03  5215.5 1750.10  5235.5 1751.75  5245.5 1753.64
#Mann=7,-1,0
  4747.0    0.07       0  4826.4     0.1       0  4949.1    0.07       0
  4952.8     0.1       0  5003.5    0.05       0  5007.5     0.1       0
  5096.9    0.07       0
Bank Sta=5003.5,5007.5
Exp/Cntr=0.3,0.1

Type RM Length L Ch R = 1,39,0,0,0
BEGIN DESCRIPTION:
Stream0077 0.0
END DESCRIPTION:
XS GIS Cut Line= 4
      1996975.12     13930991.70      1996815.58     13931185.99
      1996809.65     13931342.02      1997013.51     13931688.91
#Sta/Elev= 30
  4708.8 1738.53  4853.8 1727.91  4874.6 1724.49  4881.3 1725.60  4895.4 1725.22
  4938.5 1721.94  4956.7 1718.07  4962.2 1718.07  4979.2 1711.11  4987.2 1710.54
  4987.5 1710.04  4991.2 1710.54  4999.2 1710.95  5049.3 1719.30  5102.4 1721.58
  5152.6 1724.29  5174.1 1723.03  5232.8 1724.63  5371.4 1727.50  5392.9 1729.67
  5398.7 1732.42  5408.5 1732.86  5414.3 1734.90  5421.4 1735.59  5451.5 1735.73
  5457.3 1737.02  5467.1 1736.23  5472.9 1737.28  5488.6 1736.59  5518.7 1738.74
#Mann=5,-1,0
  4708.8    0.07       0  4987.2    0.05       0  4991.2    0.07       0
  5102.4     0.1       0  5232.8    0.07       0
Bank Sta=4987.2,4991.2
Exp/Cntr=0.3,0.1

Chan Stop Cuts=-1