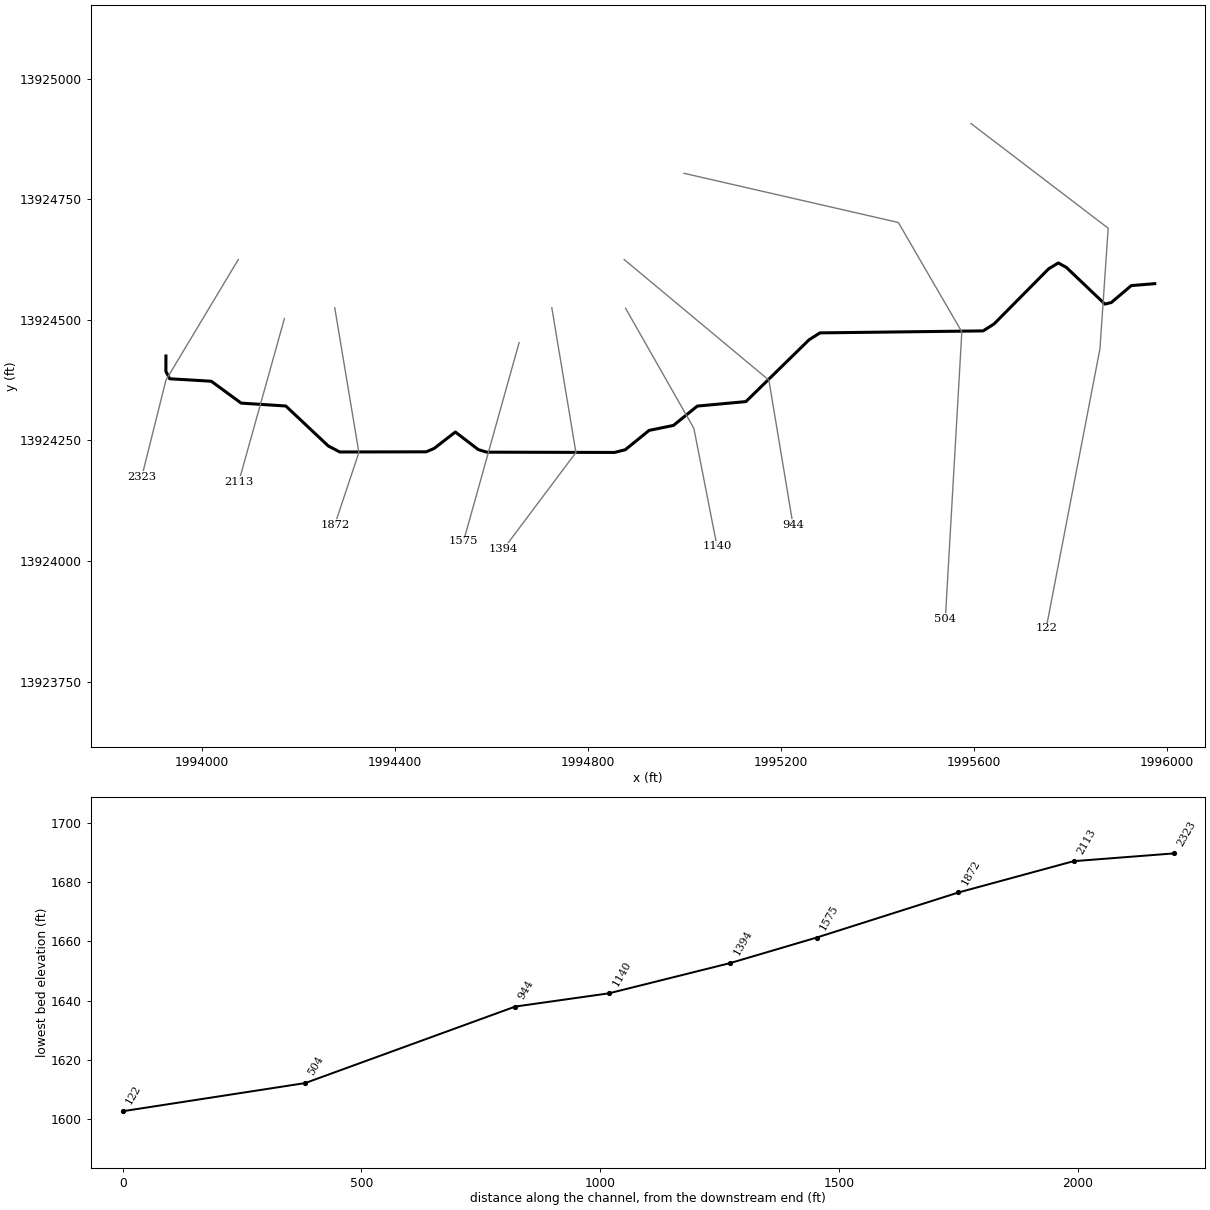
--- Stream0078.prj (project) ---

Proj Title=Stream0078 Base Level Engineering
Current Plan=p01
Default Exp/Contr=0.3,0.1
English Units
Geom File=g01
Flow File=f01
Plan File=p01
BEGIN DESCRIPTION:
Stream0078
END DESCRIPTION:

--- Stream0078.p01 (plan) ---

Plan Title=Multiple Run
Short Identifier=Multiple
Geom File=g01
Flow File=f01
Subcritical Flow
K Sum by GR= 0
Std Step Tol= 0.01
Critical Tol= 0.01
Num of Std Step Trials= 20
Max Error Tol= 0.3
Flow Tol Ratio= 0.001
Split Flow NTrial= 30
Split Flow Tol= 0.02
Split Flow Ratio= 0.02
Log Output Level= 0
Friction Slope Method= 1
Unsteady Friction Slope Method= 2
Unsteady Bridges Friction Slope Method= 1
Parabolic Critical Depth
Global Vel Dist=  1 , 1 , 1
Global Log Level= 0
CheckData=True
Encroach Param= -1, 0, 0, 0
BEGIN DESCRIPTION:
Multiple Run
END DESCRIPTION:

--- Stream0078.f01 (steady flow) ---

Flow Title=Multiple
Number of Profiles=7
Profile Names=10-year,25-year,50-year,1pct_min,100-year,1pct_plu,500-year
River Rch & RM= Stream0078,Reach-1,2323
     521     871    1200     807    1611    3213    2868
Boundary for River Rch & Prof#=Stream0078,Reach-1,1
Up Type=0
Dn Type=3
Dn Slope=0.005
Boundary for River Rch & Prof#=Stream0078,Reach-1,2
Up Type=0
Dn Type=3
Dn Slope=0.005
Boundary for River Rch & Prof#=Stream0078,Reach-1,3
Up Type=0
Dn Type=3
Dn Slope=0.005
Boundary for River Rch & Prof#=Stream0078,Reach-1,4
Up Type=0
Dn Type=3
Dn Slope=0.005
Boundary for River Rch & Prof#=Stream0078,Reach-1,5
Up Type=0
Dn Type=3
Dn Slope=0.005
Boundary for River Rch & Prof#=Stream0078,Reach-1,6
Up Type=0
Dn Type=3
Dn Slope=0.005
Boundary for River Rch & Prof#=Stream0078,Reach-1,7
Up Type=0
Dn Type=3
Dn Slope=0.005

--- Stream0078.g01 (geometry) ---

Geom Title=Existing Conditions

River Reach=Stream0078,Reach-1
Reach XY= 30
      1993925.00     13924425.00      1993924.92     13924393.10
      1993932.76     13924377.84      1994018.99     13924372.69
      1994080.97     13924327.35      1994173.50     13924321.38
      1994261.69     13924238.40      1994285.44     13924226.05
      1994464.56     13924226.38      1994481.18     13924233.45
      1994525.00     13924267.44      1994572.55     13924231.02
      1994590.16     13924225.66      1994854.97     13924225.06
      1994877.35     13924230.71      1994926.74     13924270.81
      1994977.18     13924281.11      1995026.59     13924321.17
      1995127.43     13924330.52      1995258.24     13924458.57
      1995280.85     13924472.94      1995619.15     13924477.06
      1995641.76     13924491.43      1995755.00     13924605.78
      1995775.00     13924617.91      1995791.67     13924608.74
      1995871.61     13924532.62      1995884.90     13924535.90
      1995926.36     13924570.98      1995975.00     13924575.00

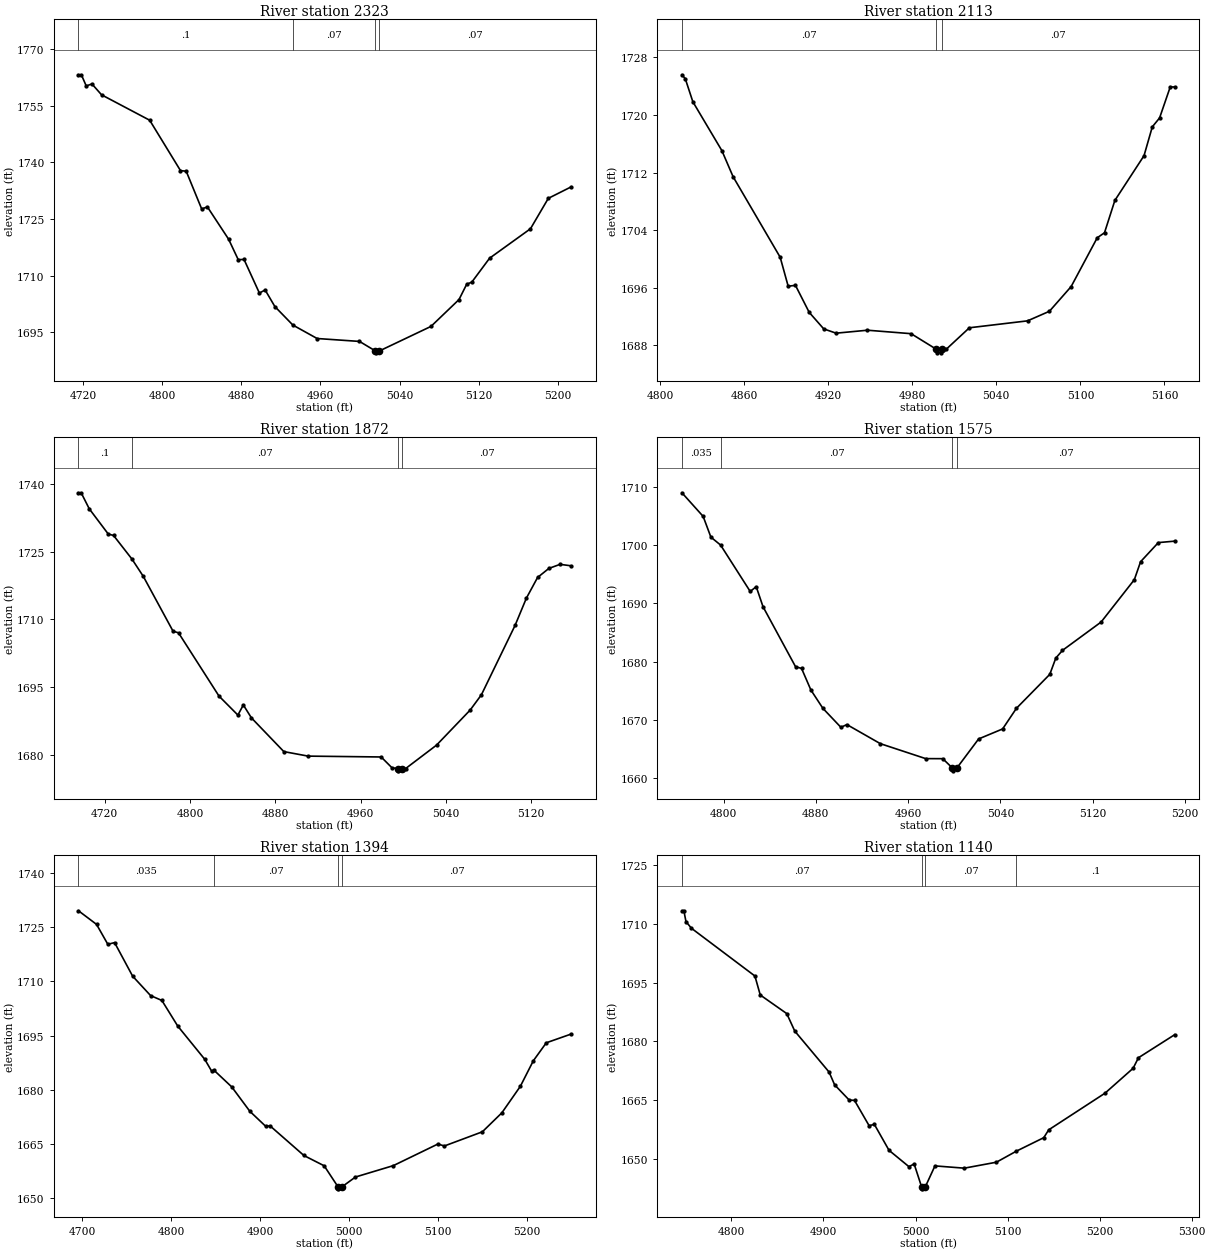
Type RM Length L Ch R = 1,2323,210,210,210
BEGIN DESCRIPTION:
Stream0078 5.0
END DESCRIPTION:
XS GIS Cut Line= 3
      1994075.00     13924625.00      1993925.00     13924375.00
      1993875.00     13924175.01
#Sta/Elev= 30
  4715.6 1763.14  4718.5 1763.14  4723.4 1760.20  4729.2 1760.71  4738.9 1757.84
  4787.5 1751.12  4818.6 1737.80  4824.4 1737.63  4840.0 1727.66  4845.8 1728.19
  4867.2 1719.66  4876.9 1714.26  4882.8 1714.29  4898.3 1705.41  4904.1 1706.23
  4913.9 1701.85  4932.1 1696.95  4956.6 1693.39  4999.4 1692.62  5015.5 1690.10
  5015.7 1689.60  5019.5 1690.10  5071.6 1696.59  5099.9 1703.69  5107.7 1707.76
  5112.8 1708.29  5130.8 1714.63  5172.1 1722.42  5190.1 1730.46  5213.3 1733.51
#Mann=4,-1,0
  4715.6     0.1       0  4932.1    0.07       0  5015.5    0.05       0
  5019.5    0.07       0
Bank Sta=5015.5,5019.5
Exp/Cntr=0.3,0.1

Type RM Length L Ch R = 1,2113,241,241,241
BEGIN DESCRIPTION:
Mapping XS 4d38dc78
END DESCRIPTION:
XS GIS Cut Line= 2
      1994170.58     13924502.49      1994075.91     13924163.87
#Sta/Elev= 30
  4815.7 1725.58  4818.1 1725.03  4823.5 1721.83  4844.2 1715.05  4852.2 1711.43
  4885.8 1700.25  4891.5 1696.23  4896.7 1696.35  4906.5 1692.60  4916.9 1690.30
  4925.7 1689.71  4948.1 1690.12  4979.2 1689.64  4997.2 1687.48  4997.4 1686.98
  5000.9 1686.98  5001.2 1687.48  5004.4 1687.50  5020.8 1690.46  5062.3 1691.42
  5077.9 1692.75  5093.4 1696.18  5112.0 1702.95  5117.2 1703.65  5124.6 1708.14
  5145.4 1714.35  5151.3 1718.35  5156.5 1719.59  5164.1 1723.89  5167.3 1723.89
#Mann=3,-1,0
  4815.7    0.07       0  4997.2    0.05       0  5001.2    0.07       0
Bank Sta=4997.2,5001.2
Exp/Cntr=0.3,0.1

Type RM Length L Ch R = 1,1872,297,297,297
BEGIN DESCRIPTION:
Stream0078 4.0
END DESCRIPTION:
XS GIS Cut Line= 3
      1994275.00     13924524.99      1994325.00     13924225.00
      1994275.01     13924075.04
#Sta/Elev= 30
  4695.4 1738.01  4697.9 1738.01  4705.5 1734.46  4723.3 1728.88  4728.3 1728.55
  4745.6 1723.31  4756.2 1719.49  4784.1 1707.35  4789.2 1707.00  4827.2 1692.98
  4844.9 1688.78  4850.0 1691.02  4857.6 1688.16  4888.0 1680.69  4910.8 1679.69
  4979.3 1679.50  4989.4 1677.11  4995.0 1676.93  4995.2 1676.43  4999.0 1676.93
  5002.2 1676.93  5031.2 1682.12  5062.8 1689.90  5073.3 1693.27  5104.9 1708.65
  5115.5 1714.68  5126.0 1719.26  5136.6 1721.26  5147.1 1722.16  5157.6 1721.83
#Mann=4,-1,0
  4695.4     0.1       0  4745.6    0.07       0  4995.0    0.05       0
  4999.0    0.07       0
Bank Sta=4995,4999
Exp/Cntr=0.3,0.1

Type RM Length L Ch R = 1,1575,181,181,181
BEGIN DESCRIPTION:
Mapping XS 0bc198df
END DESCRIPTION:
XS GIS Cut Line= 2
      1994657.15     13924452.70      1994542.06     13924041.29
#Sta/Elev= 30
  4763.9 1709.01  4782.3 1704.95  4789.0 1701.39  4797.4 1700.03  4823.1 1692.05
  4828.3 1692.88  4834.2 1689.43  4862.4 1679.12  4867.6 1678.83  4875.7 1675.12
  4886.1 1671.97  4901.7 1668.71  4906.9 1669.18  4935.9 1665.90  4975.2 1663.33
  4990.0 1663.32  4998.3 1661.73  4998.6 1661.23  5002.3 1661.73  5021.1 1666.71
  5041.9 1668.43  5053.9 1671.98  5082.8 1677.81  5088.0 1680.60  5093.8 1681.93
  5127.3 1686.80  5156.1 1694.08  5161.5 1697.16  5176.9 1700.45  5191.1 1700.70
#Mann=4,-1,0
  4763.9   0.035       0  4797.4    0.07       0  4998.3    0.05       0
  5002.3    0.07       0
Bank Sta=4998.3,5002.3
Exp/Cntr=0.3,0.1

Type RM Length L Ch R = 1,1394,254,254,254
BEGIN DESCRIPTION:
Stream0078 3.0
END DESCRIPTION:
XS GIS Cut Line= 3
      1994724.99     13924525.04      1994775.00     13924225.00
      1994624.99     13924024.98
#Sta/Elev= 30
  4695.7 1729.51  4716.0 1725.75  4728.7 1720.24  4736.3 1720.71  4756.6 1711.43
  4776.8 1706.06  4789.5 1704.71  4807.3 1697.64  4837.7 1688.44  4845.3 1685.23
  4848.4 1685.35  4868.1 1680.80  4888.4 1674.07  4906.1 1669.95  4911.2 1670.03
  4949.2 1661.85  4972.0 1659.00  4987.7 1653.13  4988.0 1652.63  4991.7 1653.13
  5007.2 1655.90  5049.9 1659.06  5099.9 1665.02  5107.2 1664.48  5149.9 1668.40
  5171.8 1673.64  5192.6 1680.97  5207.2 1688.03  5221.8 1693.01  5249.9 1695.44
#Mann=4,-1,0
  4695.7   0.035       0  4848.4    0.07       0  4987.7    0.05       0
  4991.7    0.07       0
Bank Sta=4987.7,4991.7
Exp/Cntr=0.3,0.1

Type RM Length L Ch R = 1,1140,196,196,196
BEGIN DESCRIPTION:
Mapping XS 3ae2e848
END DESCRIPTION:
XS GIS Cut Line= 3
      1994877.89     13924523.97      1995019.50     13924274.96
      1995067.46     13924030.68
#Sta/Elev= 30
  4746.2 1713.31  4748.3 1713.31  4750.6 1710.55  4756.5 1708.86  4825.5 1696.68
  4831.3 1691.84  4860.1 1687.10  4868.8 1682.64  4906.1 1672.19  4912.1 1668.94
  4927.9 1665.07  4933.7 1664.98  4949.5 1658.55  4955.3 1658.85  4971.2 1652.25
  4992.8 1648.09  4998.5 1648.77  5006.6 1642.93  5006.9 1642.43  5010.6 1642.93
  5021.1 1648.28  5053.0 1647.70  5087.9 1649.22  5109.6 1652.04  5139.3 1655.47
  5144.7 1657.47  5205.9 1666.82  5236.4 1673.16  5242.2 1675.85  5281.6 1681.73
#Mann=4,-1,0
  4746.2    0.07       0  5006.6    0.05       0  5010.6    0.07       0
  5109.6     0.1       0
Bank Sta=5006.6,5010.6
Exp/Cntr=0.3,0.1

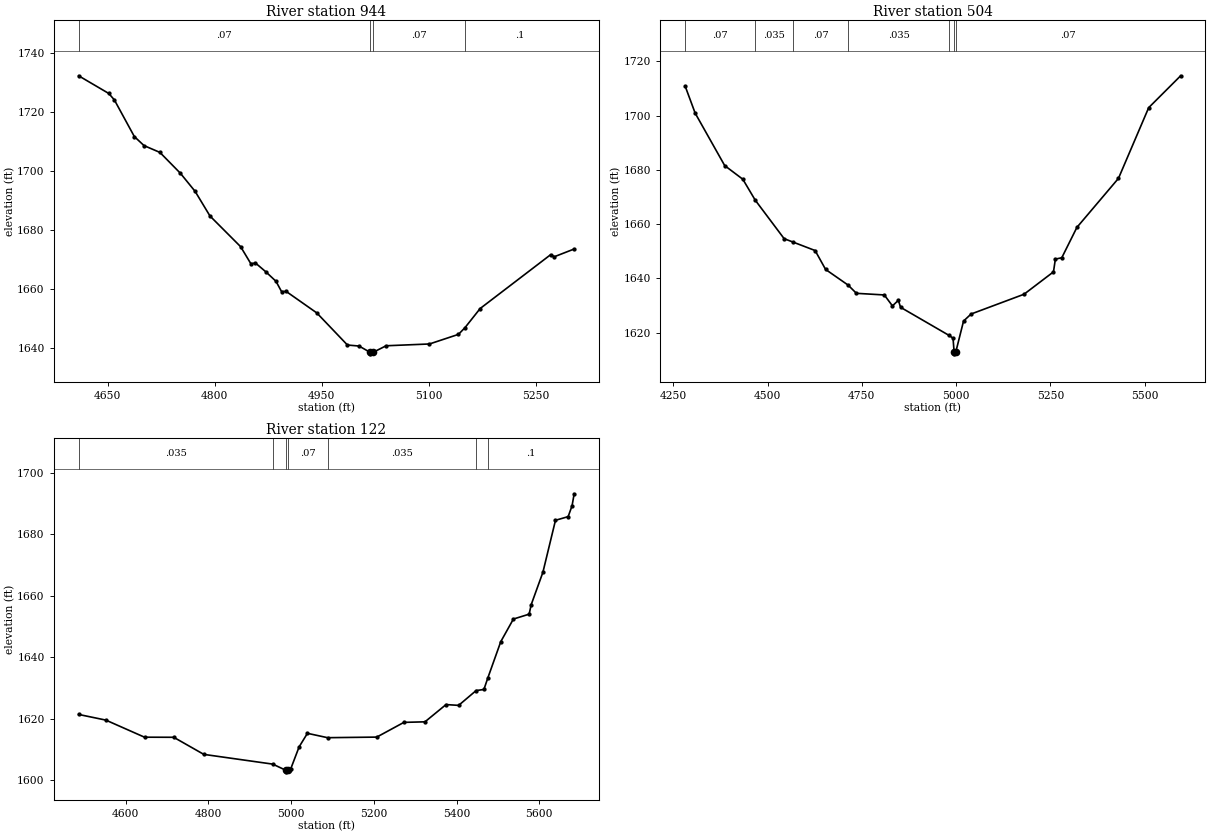
Type RM Length L Ch R = 1,944,440,440,440
BEGIN DESCRIPTION:
Stream0078 2.0
END DESCRIPTION:
XS GIS Cut Line= 3
      1994875.03     13924624.97      1995175.00     13924375.00
      1995225.00     13924075.01
#Sta/Elev= 30
  4609.2 1732.37  4651.5 1726.36  4659.3 1724.17  4687.3 1711.73  4700.9 1708.66
  4723.1 1706.36  4751.7 1699.31  4772.5 1693.12  4793.3 1684.77  4836.3 1674.34
  4850.6 1668.57  4857.1 1668.80  4871.4 1665.86  4885.8 1662.61  4893.6 1659.12
  4900.1 1659.16  4943.0 1651.87  4986.0 1640.96  5002.2 1640.62  5017.9 1638.47
  5018.2 1637.97  5021.9 1638.47  5040.2 1640.71  5101.0 1641.32  5141.6 1644.58
  5150.8 1646.87  5172.0 1653.35  5270.9 1671.65  5275.9 1670.93  5303.8 1673.56
#Mann=4,-1,0
  4609.2    0.07       0  5017.9    0.05       0  5021.9    0.07       0
  5150.8     0.1       0
Bank Sta=5017.9,5021.9
Exp/Cntr=0.3,0.1

Type RM Length L Ch R = 1,504,382,382,382
BEGIN DESCRIPTION:
Stream0078 1.0
END DESCRIPTION:
XS GIS Cut Line= 4
      1994999.01     13924803.79      1995443.37     13924701.84
      1995575.00     13924475.00      1995540.84     13923880.45
#Sta/Elev= 30
  4281.4 1710.97  4308.1 1700.94  4386.4 1681.60  4434.4 1676.57  4467.3 1668.86
  4544.0 1654.64  4567.8 1653.38  4626.1 1650.27  4653.9 1643.30  4713.3 1637.55
  4735.6 1634.49  4809.5 1633.89  4831.1 1629.86  4846.8 1631.91  4852.6 1629.34
  4981.5 1618.94  4991.7 1617.93  4994.7 1612.67  4994.9 1612.17  4998.7 1612.67
  5019.6 1624.26  5039.6 1626.86  5179.9 1634.15  5258.0 1642.41  5263.0 1647.11
  5280.0 1647.61  5320.1 1658.81  5430.3 1676.90  5510.4 1702.97  5595.1 1714.73
#Mann=7,-1,0
  4281.4    0.07       0  4467.3   0.035       0  4567.8    0.07       0
  4713.3   0.035       0  4981.5    0.07       0  4994.7    0.05       0
  4998.7    0.07       0
Bank Sta=4994.7,4998.7
Exp/Cntr=0.3,0.1

Type RM Length L Ch R = 1,122,0,0,0
BEGIN DESCRIPTION:
Stream0078 0.0
END DESCRIPTION:
XS GIS Cut Line= 4
      1995593.90     13924907.06      1995878.43     13924689.90
      1995861.39     13924440.14      1995749.87     13923860.65
#Sta/Elev= 30
  4486.1 1621.35  4551.9 1619.51  4645.4 1613.95  4716.1 1613.92  4788.8 1608.36
  4955.6 1605.19  4987.3 1603.18  4987.5 1602.68  4991.3 1603.18  4999.3 1603.74
  5019.3 1610.80  5039.4 1615.21  5088.1 1613.79  5207.1 1613.98  5272.7 1618.77
  5323.7 1618.95  5374.6 1624.56  5405.1 1624.30  5447.4 1629.12  5466.2 1629.47
  5475.6 1633.19  5507.0 1645.03  5537.5 1652.38  5575.6 1653.97  5580.6 1657.07
  5608.8 1667.56  5639.3 1684.51  5669.9 1685.69  5679.4 1689.23  5684.5 1693.13
#Mann=7,-1,0
  4486.1   0.035       0  4955.6    0.07       0  4987.3    0.05       0
  4991.3    0.07       0  5088.1   0.035       0  5447.4    0.07       0
  5475.6     0.1       0
Bank Sta=4987.3,4991.3
Exp/Cntr=0.3,0.1

Chan Stop Cuts=-1