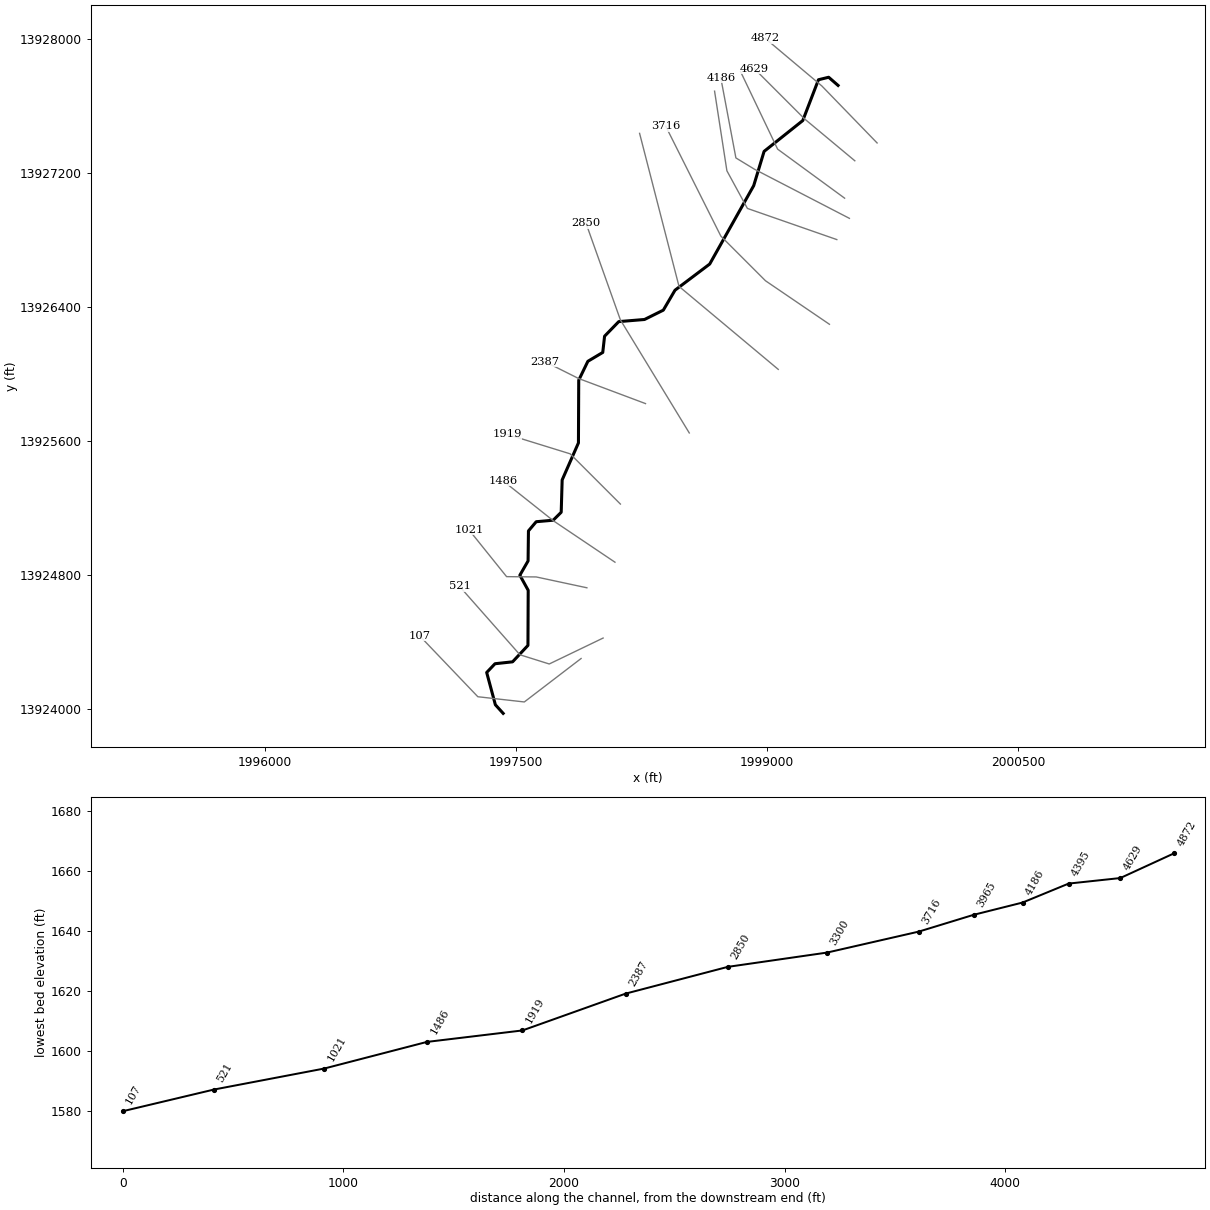
--- Stream0079.prj (project) ---

Proj Title=Stream0079 Base Level Engineering
Current Plan=p01
Default Exp/Contr=0.3,0.1
English Units
Geom File=g01
Flow File=f01
Plan File=p01
Y Axis Title=Elevation
X Axis Title(PF)=Main Channel Distance
X Axis Title(XS)=Station
BEGIN DESCRIPTION:
Stream0079
END DESCRIPTION:
DSS Export Rating Curves= 0
DSS Export Rating Curve Sorted= 0
DSS Export Volume Flow Curves= 0
DXF OffsetX= 0
DXF OffsetY= 0
DXF ScaleX= 1
DXF ScaleY= 10

--- Stream0079.p01 (plan) ---

Plan Title=Multiple Run
Short Identifier=Multiple
Geom File=g01
Flow File=f01
Subcritical Flow
K Sum by GR= 0
Std Step Tol= 0.01
Critical Tol= 0.01
Num of Std Step Trials= 20
Max Error Tol= 0.3
Flow Tol Ratio= 0.001
Split Flow NTrial= 30
Split Flow Tol= 0.02
Split Flow Ratio= 0.02
Log Output Level= 0
Friction Slope Method= 1
Unsteady Friction Slope Method= 2
Unsteady Bridges Friction Slope Method= 1
Parabolic Critical Depth
Global Vel Dist=  1 , 1 , 1
Global Log Level= 0
CheckData=True
Encroach Param= -1, 0, 0, 0
BEGIN DESCRIPTION:
Multiple Run
END DESCRIPTION:

--- Stream0079.f01 (steady flow) ---

Flow Title=Multiple
Number of Profiles=7
Profile Names=10-year,25-year,50-year,1pct_min,100-year,1pct_plu,500-year
River Rch & RM= Stream0079,Reach-1,4872
    1148    2000    2833    1949    3889    7760    7269
River Rch & RM= Stream0079,Reach-1,2850
    1213    2115    2996    2060    4111    8202    7677
Boundary for River Rch & Prof#=Stream0079,Reach-1,1
Up Type=0
Dn Type=3
Dn Slope=0.005
Boundary for River Rch & Prof#=Stream0079,Reach-1,2
Up Type=0
Dn Type=3
Dn Slope=0.005
Boundary for River Rch & Prof#=Stream0079,Reach-1,3
Up Type=0
Dn Type=3
Dn Slope=0.005
Boundary for River Rch & Prof#=Stream0079,Reach-1,4
Up Type=0
Dn Type=3
Dn Slope=0.005
Boundary for River Rch & Prof#=Stream0079,Reach-1,5
Up Type=0
Dn Type=3
Dn Slope=0.005
Boundary for River Rch & Prof#=Stream0079,Reach-1,6
Up Type=0
Dn Type=3
Dn Slope=0.005
Boundary for River Rch & Prof#=Stream0079,Reach-1,7
Up Type=0
Dn Type=3
Dn Slope=0.005

--- Stream0079.g01 (geometry) ---

Geom Title=Existing Conditions
Program Version=4.10

River Reach=Stream0079      ,Reach-1
Reach XY= 30
        1999425.       13927725.      1999368.89      13927773.8
      1999307.83     13927758.96      1999214.25     13927515.29
      1998983.13     13927331.07      1998921.17     13927126.58
      1998658.36     13926658.32      1998451.17     13926502.13
      1998381.34     13926383.02      1998269.07     13926327.25
      1998115.18     13926314.53      1998030.54     13926227.38
      1998019.71     13926130.48      1997930.77     13926077.53
       1997876.2      13925964.5      1997874.48     13925590.22
      1997777.26     13925369.06      1997771.56     13925176.22
      1997723.75     13925128.51      1997622.29     13925119.59
      1997575.98     13925064.73      1997573.76      13924885.5
       1997524.6       13924800.      1997574.46     13924709.79
      1997572.95     13924380.84      1997481.19     13924282.86
      1997376.22     13924271.47      1997326.53     13924219.17
      1997378.39      13924026.4        1997425.       13923975.

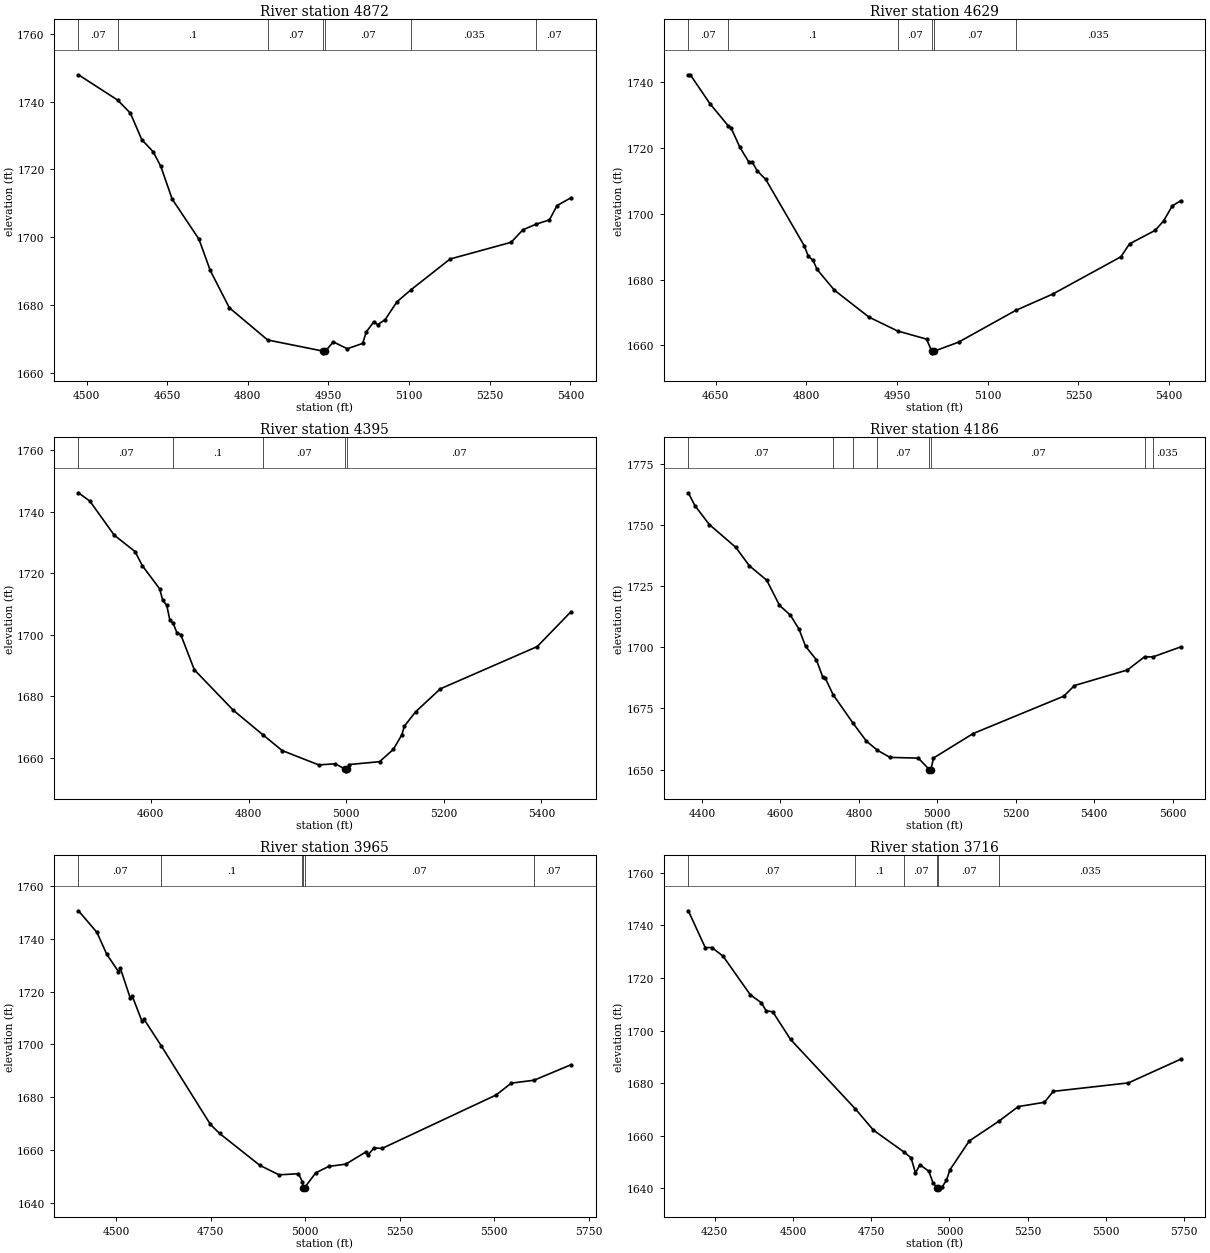
Type RM Length L Ch R = 1 ,4872    ,243,243,243
BEGIN DESCRIPTION:
Stream0079 11.0
END DESCRIPTION:
XS GIS Cut Line= 3
      1999658.05     13927381.43       1999328.2      13927721.7
      1998989.86     13928006.25
#Sta/Elev= 30
    4485 1747.89  4557.9 1740.42  4581.6 1736.56  4602.7 1728.78  4624.1 1725.15
  4638.2 1720.85  4659.3 1711.22    4709 1699.44  4730.1 1690.18  4765.6 1679.18
  4836.9 1669.68  4940.3 1666.39  4940.5 1665.89  4944.3 1666.39  4958.9 1669.12
    4985  1667.1  5013.6 1668.67  5020.2 1672.01  5034.5  1675.1  5041.5 1674.19
  5055.3 1675.67  5077.4 1680.95  5103.8 1684.53  5176.2 1693.56  5289.8 1698.49
  5311.5 1702.16  5336.4 1703.85  5360.9 1705.09  5375.2 1709.33    5401 1711.62
#Mann= 7 ,-1 , 0
    4485     .07       0  4557.9      .1       0  4836.9     .07       0
  4940.3     .05       0  4944.3     .07       0  5103.8    .035       0
  5336.4     .07       0
Bank Sta=4940.3,4944.3
XS Rating Curve= 0 ,0
Exp/Cntr=0.3,0.1

Type RM Length L Ch R = 1 ,4629    ,234,234,234
BEGIN DESCRIPTION:
Stream0079 10.0
END DESCRIPTION:
XS GIS Cut Line= 3
      1999525.02     13927274.98        1999225.       13927525.
        1998925.       13927825.
#Sta/Elev= 30
  4604.7 1742.33    4608 1742.33  4640.5 1733.53  4670.7  1726.8  4675.7 1726.05
    4690 1720.26  4704.3 1715.92  4710.8 1715.64  4718.6 1713.11  4732.9 1710.45
  4796.7 1690.22  4803.2 1687.06    4811 1685.87  4817.6  1683.1  4846.2 1676.79
  4903.5 1668.57    4951 1664.33  4998.8 1661.86  5007.4 1658.18  5007.6 1657.68
  5011.4 1658.18  5051.8 1660.93  5146.1 1670.57  5207.4 1675.55  5320.5 1686.93
  5334.7 1690.86  5377.1 1694.96  5391.2 1697.88  5405.4 1702.41  5419.5 1704.01
#Mann= 6 ,-1 , 0
  4604.7     .07       0  4670.7      .1       0    4951     .07       0
  5007.4     .05       0  5011.4     .07       0  5146.1    .035       0
Bank Sta=5007.4,5011.4
XS Rating Curve= 0 ,0
Exp/Cntr=0.3,0.1

Type RM Length L Ch R = 1 ,4395    ,209,209,209
BEGIN DESCRIPTION:
Mapping XS 4d30a690
END DESCRIPTION:
XS GIS Cut Line= 3
      1999464.04     13927051.72      1999063.86     13927344.62
      1998842.79     13927807.42
#Sta/Elev= 30
  4451.7 1746.18  4475.3 1743.42  4524.9 1732.42  4567.8 1727.05  4582.4 1722.52
    4618 1714.97  4624.1 1711.38  4632.6 1709.56  4638.8 1704.91  4645.8 1703.72
  4653.5 1700.65  4661.2 1700.11    4689 1688.68  4768.5 1675.58    4829 1667.61
  4868.9 1662.44  4943.8 1657.77  4977.8 1658.13  4998.4 1656.34  4998.7 1655.84
  5002.4 1656.34    5006 1657.88  5068.5 1658.82  5096.7 1662.81  5113.8 1667.48
  5119.4 1670.38  5142.1 1674.99    5193 1682.49  5391.3  1696.2  5460.5 1707.53
#Mann= 5 ,-1 , 0
  4451.7     .07       0  4645.8      .1       0    4829     .07       0
  4998.4     .05       0  5002.4     .07       0
Bank Sta=4998.4,5002.4
XS Rating Curve= 0 ,0
Exp/Cntr=0.3,0.1

Type RM Length L Ch R = 1 ,4186    ,221,221,221
BEGIN DESCRIPTION:
Stream0079 9.0
END DESCRIPTION:
XS GIS Cut Line= 4
      1999492.64     13926931.18        1998925.       13927225.
      1998814.77     13927292.12      1998724.37     13927771.44
#Sta/Elev= 30
    4365 1763.16  4381.7 1757.93  4418.6 1750.18  4486.2 1740.85  4520.2  1733.4
    4565 1727.41  4597.5 1717.17  4625.2 1713.15  4647.4 1707.41  4663.9 1700.45
  4691.6 1694.89  4708.1 1687.77  4713.8 1687.56  4734.2 1680.67  4783.9 1669.27
  4818.8 1661.74  4847.1 1657.94  4879.6 1655.01  4951.6 1654.72  4979.7 1650.02
  4979.9 1649.52  4983.7 1650.02  4990.3 1654.75  5091.3 1664.75  5322.6 1680.04
  5349.9 1684.39    5485 1690.75  5528.8 1696.15  5550.2  1696.1    5621 1700.18
#Mann= 8 ,-1 , 0
    4365     .07       0  4734.2    .035       0  4783.9      .1       0
  4847.1     .07       0  4979.7     .05       0  4983.7     .07       0
  5528.8     .07       0  5550.2    .035       0
Bank Sta=4979.7,4983.7
XS Rating Curve= 0 ,0
Exp/Cntr=0.3,0.1

Type RM Length L Ch R = 1 ,3965    ,249,249,249
BEGIN DESCRIPTION:
Mapping XS c351ef89
END DESCRIPTION:
XS GIS Cut Line= 4
      1999417.46     13926804.44      1998883.45      13926990.5
      1998761.03     13927215.34      1998687.43     13927690.88
#Sta/Elev= 30
  4400.7 1750.52  4449.5 1742.36  4475.3 1734.14  4506.3 1727.57  4511.6 1728.77
  4537.4 1717.62  4542.7 1718.41  4568.5 1708.83  4573.8 1709.59  4619.2 1699.59
  4749.7  1669.8  4773.9 1666.39  4879.8  1654.4  4930.9 1650.74  4982.7 1651.16
  4993.1 1648.08  4995.1 1645.95  4995.3 1645.45  4999.1 1645.95  5028.2 1651.48
  5062.6 1653.92  5107.9 1654.79  5160.4 1659.35  5166.1 1658.16  5182.2 1660.89
  5204.1 1660.74  5505.2  1680.9  5545.7 1685.39  5605.8 1686.49  5703.4 1692.33
#Mann= 6 ,-1 , 0
  4400.7     .07       0  4619.2      .1       0  4993.1     .07       0
  4995.1     .05       0  4999.1     .07       0  5605.8     .07       0
Bank Sta=4995.1,4999.1
XS Rating Curve= 0 ,0
Exp/Cntr=0.3,0.1

Type RM Length L Ch R = 1 ,3716    ,416,416,416
BEGIN DESCRIPTION:
Stream0079 8.0
END DESCRIPTION:
XS GIS Cut Line= 4
      1999373.36     13926298.63      1998991.45     13926558.55
        1998725.       13926825.      1998395.82     13927481.29
#Sta/Elev= 30
    4166 1745.52  4220.1 1731.51  4241.1 1731.56    4277 1728.28  4363.8 1713.63
  4399.7 1710.52  4414.6 1707.49  4435.6 1707.14  4492.5 1696.63  4699.5 1670.24
  4757.3 1662.15  4855.7 1653.76  4877.5 1651.63  4891.6 1645.86  4905.8 1649.02
  4934.1 1646.53  4948.2 1641.99  4960.4 1640.35  4960.6 1639.85  4964.4 1640.35
  4976.5 1640.55  4990.6 1643.09  5001.2 1647.01  5063.4 1658.05  5158.3 1665.59
  5219.8 1671.11  5303.6 1672.74  5331.5 1676.89  5571.6 1680.11    5739 1689.13
#Mann= 6 ,-1 , 0
    4166     .07       0  4699.5      .1       0  4855.7     .07       0
  4960.4     .05       0  4964.4     .07       0  5158.3    .035       0
Bank Sta=4960.4,4964.4
XS Rating Curve= 0 ,0
Exp/Cntr=0.3,0.1

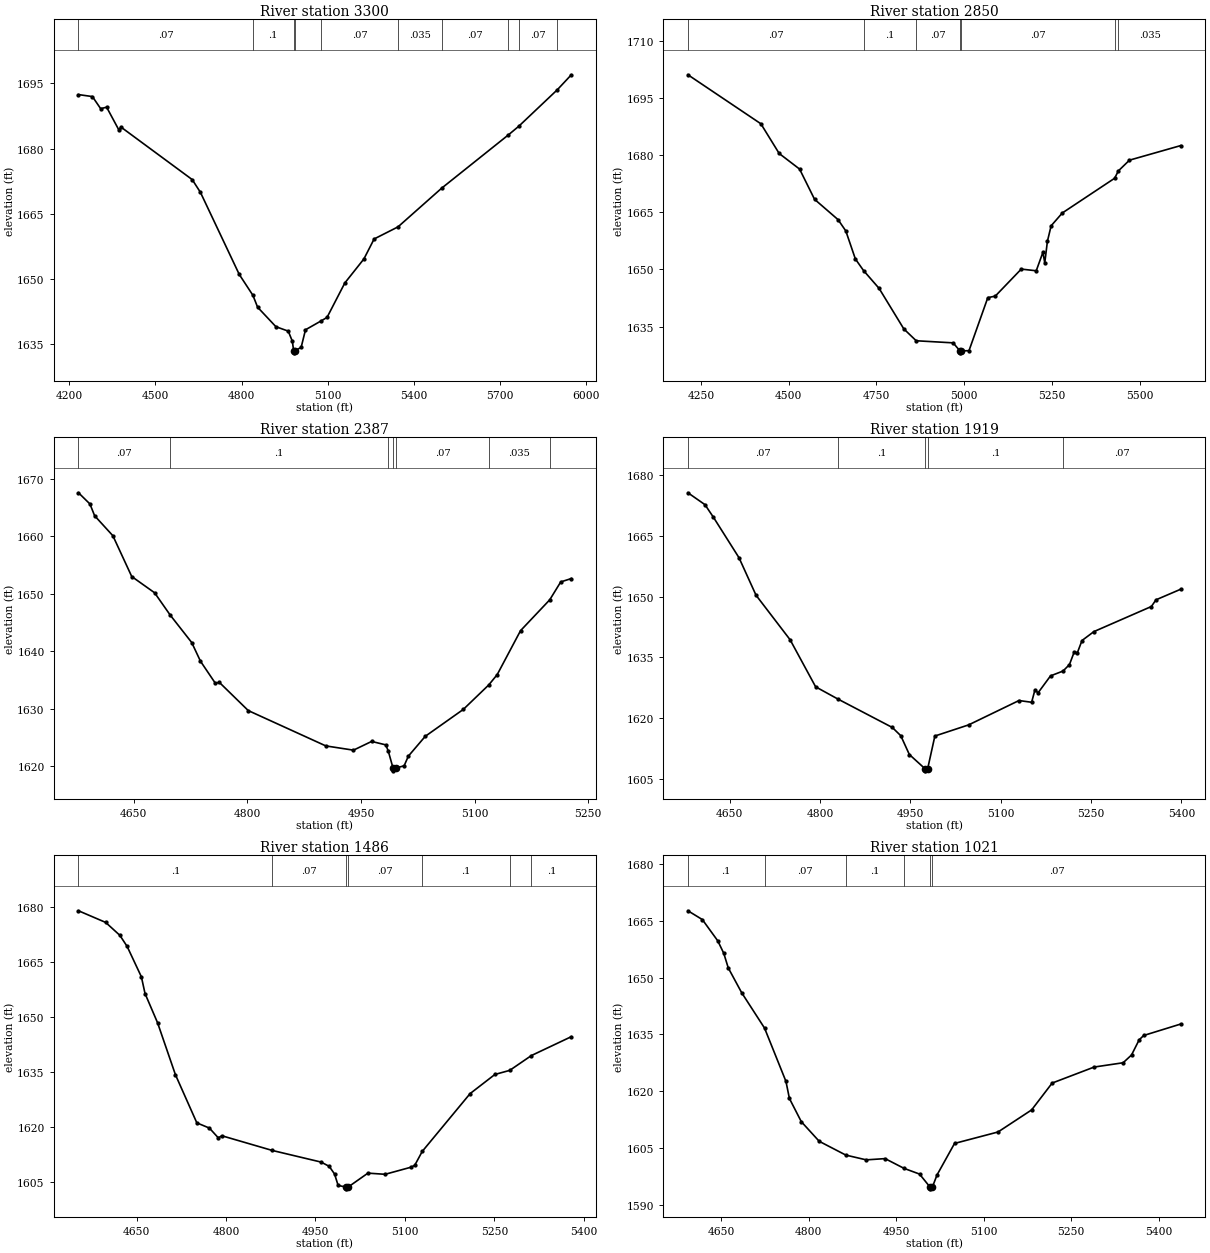
Type RM Length L Ch R = 1 ,3300    ,450,450,450
BEGIN DESCRIPTION:
Stream0079 7.0
END DESCRIPTION:
XS GIS Cut Line= 3
      1999067.74      13926029.3        1998475.       13926525.
      1998239.68     13927438.79
#Sta/Elev= 30
  4232.2 1692.44  4280.7 1691.98  4309.4 1689.19  4330.2 1689.53  4373.1 1684.24
  4379.6 1684.97  4628.2 1672.83  4656.8 1669.89  4792.1 1650.94  4839.7 1646.12
  4855.9 1643.39  4919.7 1638.89  4962.6 1637.87  4976.9 1635.55  4981.4 1633.36
  4981.7 1632.86  4985.4 1633.36  5007.5  1634.1  5022.7 1638.18  5076.7 1640.21
  5097.8 1641.04  5159.8 1648.99  5226.2 1654.53  5261.7 1659.13  5344.9 1661.92
  5496.8 1670.84  5729.3 1683.14  5764.9  1685.1  5899.8 1693.56  5948.5 1697.01
#Mann= 10 ,-1 , 0
  4232.2     .07       0  4839.7      .1       0  4981.4     .05       0
  4985.4      .1       0  5076.7     .07       0  5344.9    .035       0
  5496.8     .07       0  5729.3    .035       0  5764.9     .07       0
  5899.8    .035       0
Bank Sta=4981.4,4985.4
XS Rating Curve= 0 ,0
Exp/Cntr=0.3,0.1

Type RM Length L Ch R = 1 ,2850    ,463,463,463
BEGIN DESCRIPTION:
Stream0079 6.0
END DESCRIPTION:
XS GIS Cut Line= 3
      1998536.34      13925649.7        1998125.       13926325.
      1997919.31     13926902.98
#Sta/Elev= 30
  4213.2 1701.08    4421 1688.22  4473.2 1680.42  4531.3 1676.33    4574 1668.39
  4640.9 1663.06    4663  1660.1  4690.2 1652.75  4713.6 1649.69  4757.9 1645.01
  4828.3 1634.38  4863.6 1631.27  4968.8 1630.72  4988.3  1628.6  4988.6  1628.1
  4992.3  1628.6    5014 1628.67  5067.6 1642.59  5088.8 1642.98  5162.9 1650.08
  5205.6 1649.64  5224.6 1654.48  5229.9 1651.72  5237.4 1657.37    5248 1661.44
  5279.9 1664.81  5428.9 1673.92  5439.6 1675.85  5471.2 1678.67  5617.4  1682.5
#Mann= 7 ,-1 , 0
  4213.2     .07       0  4713.6      .1       0  4863.6     .07       0
  4988.3     .05       0  4992.3     .07       0  5428.9     .07       0
  5439.6    .035       0
Bank Sta=4988.3,4992.3
XS Rating Curve= 0 ,0
Exp/Cntr=0.3,0.1

Type RM Length L Ch R = 1 ,2387    ,468,468,468
BEGIN DESCRIPTION:
Stream0079 5.0
END DESCRIPTION:
XS GIS Cut Line= 3
      1998274.97     13925825.01        1997875.       13925975.
      1997674.98     13926075.01
#Sta/Elev= 30
  4576.9  1667.6    4592 1665.65  4598.2  1663.6  4622.3 1660.12  4647.2 1653.02
  4677.4 1650.19  4698.1 1646.29  4726.4 1641.53    4738 1638.27  4757.5 1634.46
  4762.9 1634.59  4801.1 1629.68  4903.5 1623.53    4940 1622.79    4964 1624.31
  4982.7 1623.71    4986 1622.62  4992.2 1619.69  4992.5 1619.19  4996.4 1619.69
  5006.9 1620.07  5012.5 1621.75  5034.8  1625.2  5085.1 1629.89  5118.6 1634.14
  5129.8 1635.94  5160.6 1643.59  5199.2 1648.97  5213.7 1652.08  5227.7 1652.67
#Mann= 7 ,-1 , 0
  4576.9     .07       0  4698.1      .1       0    4986     .07       0
  4992.2     .05       0  4996.4     .07       0  5118.6    .035       0
  5199.2     .07       0
Bank Sta=4992.2,4996.4
XS Rating Curve= 0 ,0
Exp/Cntr=0.3,0.1

Type RM Length L Ch R = 1 ,1919    ,433,433,433
BEGIN DESCRIPTION:
Stream0079 4.0
END DESCRIPTION:
XS GIS Cut Line= 3
      1998124.98     13925225.02        1997825.       13925525.
      1997448.34     13925641.48
#Sta/Elev= 30
  4580.4  1675.7  4608.7 1672.76  4622.8 1669.63  4665.2 1659.64  4693.5 1650.36
  4750.1 1639.34  4792.5  1627.7  4829.1 1624.71  4919.8 1617.65  4933.9 1615.61
  4948.1 1610.96  4974.3 1607.42  4974.5 1606.92  4978.5 1607.42  4990.5 1615.53
  5046.5 1618.28  5130.2 1624.31  5151.2 1623.88  5156.7 1626.93  5161.9 1626.22
  5182.6 1630.41  5203.3  1631.6    5214  1633.2  5221.9 1636.31  5227.2 1636.15
  5234.9 1639.16  5254.6 1641.36  5350.1 1647.57  5357.7 1649.22  5398.9 1651.85
#Mann= 5 ,-1 , 0
  4580.4     .07       0  4829.1      .1       0  4974.3     .05       0
  4978.5      .1       0  5203.3     .07       0
Bank Sta=4974.3,4978.5
XS Rating Curve= 0 ,0
Exp/Cntr=0.3,0.1

Type RM Length L Ch R = 1 ,1486    ,465,465,465
BEGIN DESCRIPTION:
Stream0079 3.0
END DESCRIPTION:
XS GIS Cut Line= 3
      1998092.63     13924877.77        1997725.       13925125.
      1997424.54      13925363.6
#Sta/Elev= 30
  4552.5 1679.04  4598.1 1675.86  4621.9 1672.33  4634.1  1669.3    4658    1661
  4664.1 1656.44  4685.1 1648.47  4715.1 1634.27    4751 1621.12  4772.1 1619.69
    4787 1617.03  4793.1 1617.59  4877.4 1613.59  4959.4 1610.41    4973 1609.25
    4982 1607.16    4988 1604.04  5000.6  1603.6  5000.9  1603.1  5004.9  1603.6
    5038 1607.39  5066.8 1607.07  5110.1    1609  5116.5 1609.52  5129.1 1613.32
  5209.4 1629.11    5251 1634.34  5275.8 1635.45  5312.2  1639.5  5379.2 1644.66
#Mann= 7 ,-1 , 0
  4552.5      .1       0  4877.4     .07       0  5000.6     .05       0
  5004.9     .07       0  5129.1      .1       0  5275.8     .07       0
  5312.2      .1       0
Bank Sta=5000.6,5004.9
XS Rating Curve= 0 ,0
Exp/Cntr=0.3,0.1

Type RM Length L Ch R = 1 ,1021    ,500,500,500
BEGIN DESCRIPTION:
Stream0079 2.0
END DESCRIPTION:
XS GIS Cut Line= 4
      1997925.01       13924725.      1997622.27     13924789.76
      1997445.41     13924791.53      1997221.01     13925070.65
#Sta/Elev= 30
  4593.2 1667.66  4617.9 1665.34  4644.3 1659.73  4654.6 1656.43  4662.3 1652.58
  4685.2 1646.05  4724.5 1636.68  4761.2  1622.6  4767.1  1618.1  4787.5 1611.97
  4818.2 1606.79  4863.8 1603.15  4898.8 1601.89  4931.1 1602.22  4963.5 1599.65
  4990.1 1598.14  5007.9 1594.74  5008.2 1594.24  5012.2 1594.74  5020.1 1597.91
  5050.1 1606.23  5124.6 1609.25  5182.2 1615.08  5217.4 1622.17  5289.4  1626.4
    5339 1627.53  5353.4 1629.58  5366.4 1633.56  5374.2 1634.73  5437.8 1637.76
#Mann= 6 ,-1 , 0
  4593.2      .1       0  4724.5     .07       0  4863.8      .1       0
  4963.5     .07       0  5007.9     .05       0  5012.2     .07       0
Bank Sta=5007.9,5012.2
XS Rating Curve= 0 ,0
Exp/Cntr=0.3,0.1

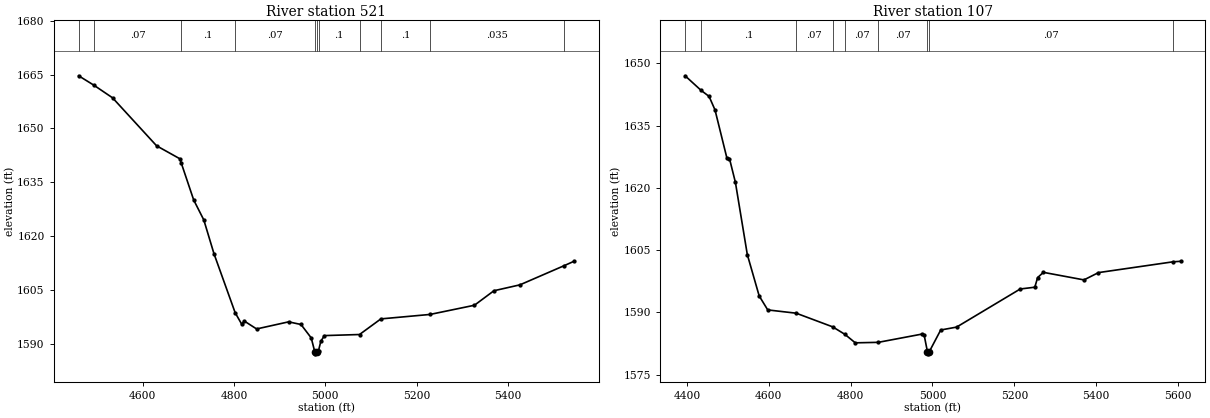
Type RM Length L Ch R = 1 ,521     ,414,414,414
BEGIN DESCRIPTION:
Stream0079 1.0
END DESCRIPTION:
XS GIS Cut Line= 4
      1998021.94     13924424.92      1997700.12     13924269.96
        1997525.       13924325.       1997164.8       13924733.
#Sta/Elev= 30
  4459.8 1664.67  4492.8 1662.08  4534.1 1658.53  4630.5 1645.17  4681.3 1641.57
  4684.5 1640.38  4711.7 1630.09  4733.9 1624.52  4756.1 1615.14  4802.5  1598.7
  4816.9 1595.48  4822.4 1596.38  4849.5 1594.17  4919.6 1596.15  4946.7 1595.41
  4969.1 1591.67    4977 1587.74  4977.2 1587.24  4981.3 1587.74    4985 1588.12
  4990.1 1590.73  4997.9 1592.32  5074.8 1592.62  5121.6 1596.97  5229.2 1598.21
  5326.4 1600.77  5369.1 1604.81    5426 1606.45  5523.2 1611.81  5544.8 1613.04
#Mann= 11 ,-1 , 0
  4459.8      .1       0  4492.8     .07       0  4684.5      .1       0
  4802.5     .07       0    4977     .05       0  4981.3     .07       0
    4985      .1       0  5074.8     .07       0  5121.6      .1       0
  5229.2    .035       0  5523.2    .063       0
Bank Sta=4977,4981.3
XS Rating Curve= 0 ,0
Exp/Cntr=0.3,0.1

Type RM Length L Ch R = 1 ,107     ,0,0,0
BEGIN DESCRIPTION:
Stream0079 0.0
END DESCRIPTION:
XS GIS Cut Line= 4
      1997890.33     13924302.66      1997551.29     13924043.18
      1997273.72     13924074.39      1996925.21     13924439.08
#Sta/Elev= 30
  4395.6 1646.99  4434.6 1643.48  4454.2 1642.02  4468.7 1638.76  4497.7 1627.18
    4504 1627.05  4518.5 1621.33  4547.6 1603.92  4576.6 1593.96  4597.5 1590.59
    4667  1589.8  4756.2 1586.51  4786.1  1584.7  4811.4 1582.66  4867.6 1582.78
  4973.9 1584.76  4979.8 1584.46  4987.7 1580.51    4988 1580.01  4992.1 1580.51
  5020.1 1585.75  5058.9 1586.45  5214.4 1595.63    5250 1596.06  5256.9 1598.38
    5271 1599.64  5370.1 1597.82  5405.6 1599.58  5587.9 1602.18  5606.3  1602.3
#Mann= 9 ,-1 , 0
  4395.6     .07       0  4434.6      .1       0    4667     .07       0
  4756.2      .1       0  4786.1     .07       0  4867.6     .07       0
  4987.7     .05       0  4992.1     .07       0  5587.9     .07       0
Bank Sta=4987.7,4992.1
XS Rating Curve= 0 ,0
Exp/Cntr=0.3,0.1

Chan Stop Cuts=-1
Use User Specified Reach Order=0
Composite Channel Slope=5