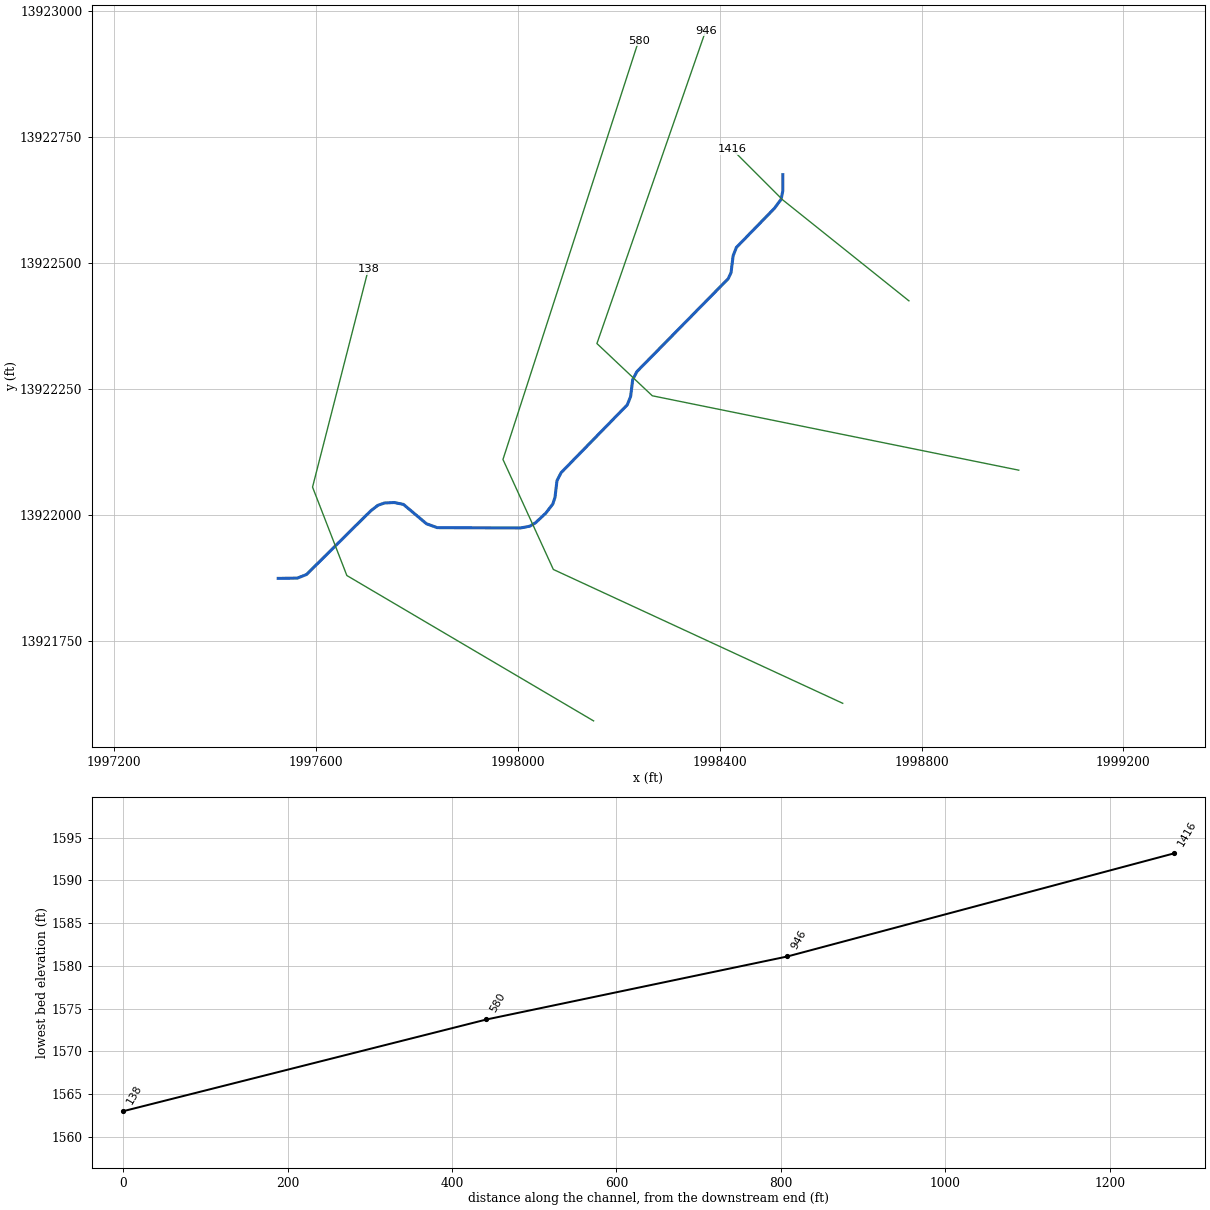
--- Stream0080.prj (project) ---

Proj Title=Stream0080 Base Level Engineering
Current Plan=p01
Default Exp/Contr=0.3,0.1
English Units
Geom File=g01
Flow File=f01
Plan File=p01
BEGIN DESCRIPTION:
Stream0080
END DESCRIPTION:

--- Stream0080.p01 (plan) ---

Plan Title=Multiple Run
Short Identifier=Multiple
Geom File=g01
Flow File=f01
Subcritical Flow
K Sum by GR= 0
Std Step Tol= 0.01
Critical Tol= 0.01
Num of Std Step Trials= 20
Max Error Tol= 0.3
Flow Tol Ratio= 0.001
Split Flow NTrial= 30
Split Flow Tol= 0.02
Split Flow Ratio= 0.02
Log Output Level= 0
Friction Slope Method= 1
Unsteady Friction Slope Method= 2
Unsteady Bridges Friction Slope Method= 1
Parabolic Critical Depth
Global Vel Dist=  1 , 1 , 1
Global Log Level= 0
CheckData=True
Encroach Param= -1, 0, 0, 0
BEGIN DESCRIPTION:
Multiple Run
END DESCRIPTION:

--- Stream0080.f01 (steady flow) ---

Flow Title=Multiple
Number of Profiles=7
Profile Names=10-year,25-year,50-year,1pct_min,100-year,1pct_plu,500-year
River Rch & RM= Stream0080,Reach-1,1416
     708    1203    1677    1137    2270    4528    4118
Boundary for River Rch & Prof#=Stream0080,Reach-1,1
Up Type=0
Dn Type=3
Dn Slope=0.005
Boundary for River Rch & Prof#=Stream0080,Reach-1,2
Up Type=0
Dn Type=3
Dn Slope=0.005
Boundary for River Rch & Prof#=Stream0080,Reach-1,3
Up Type=0
Dn Type=3
Dn Slope=0.005
Boundary for River Rch & Prof#=Stream0080,Reach-1,4
Up Type=0
Dn Type=3
Dn Slope=0.005
Boundary for River Rch & Prof#=Stream0080,Reach-1,5
Up Type=0
Dn Type=3
Dn Slope=0.005
Boundary for River Rch & Prof#=Stream0080,Reach-1,6
Up Type=0
Dn Type=3
Dn Slope=0.005
Boundary for River Rch & Prof#=Stream0080,Reach-1,7
Up Type=0
Dn Type=3
Dn Slope=0.005

--- Stream0080.g01 (geometry) ---

Geom Title=Existing Conditions

River Reach=Stream0080,Reach-1
Reach XY= 30
      1998525.00     13922675.00      1998525.07     13922643.12
      1998521.71     13922626.36      1998508.38     13922608.31
      1998433.16     13922531.05      1998426.55     13922514.36
      1998422.47     13922481.05      1998416.84     13922468.95
      1998235.78     13922284.68      1998227.53     13922268.95
      1998223.45     13922235.64      1998216.84     13922218.95
      1998085.79     13922084.66      1998077.55     13922068.91
      1998073.52     13922035.47      1998069.26     13922022.42
      1998055.41     13922004.42      1998035.12     13921985.34
      1998023.75     13921978.45      1998005.12     13921974.91
      1997840.21     13921975.54      1997818.92     13921983.19
      1997773.25     13922021.66      1997754.79     13922025.36
      1997735.62     13922024.40      1997722.70     13922019.91
      1997708.32     13922008.78      1997581.21     13921882.76
      1997563.16     13921875.59      1997525.00     13921875.00

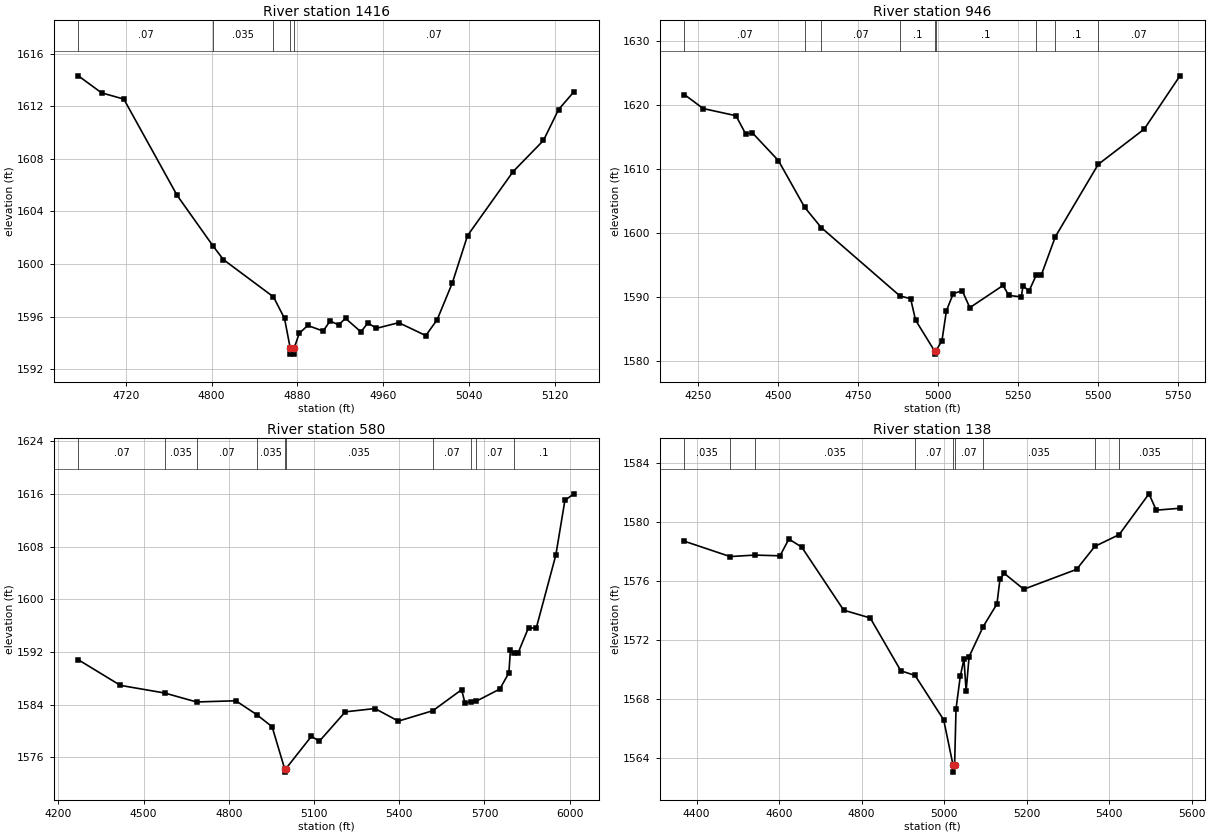
Type RM Length L Ch R = 1,1416,470,470,470
BEGIN DESCRIPTION:
Stream0080 3.0
END DESCRIPTION:
XS GIS Cut Line= 3
      1998774.98     13922425.02      1998525.00     13922625.00
      1998424.97     13922725.03
#Sta/Elev= 30
  4675.9 1614.31  4697.5 1613.02  4718.3 1612.54  4767.9 1605.23  4801.3 1601.39
  4811.1 1600.34  4857.7 1597.51  4868.0 1595.87  4873.2 1593.66  4873.4 1593.16
  4876.9 1593.16  4877.2 1593.66  4881.6 1594.73  4889.6 1595.34  4904.0 1594.91
  4910.4 1595.68  4918.4 1595.38  4924.8 1595.88  4939.2 1594.85  4945.6 1595.53
  4953.6 1595.12  4974.4 1595.55  4999.6 1594.57  5010.2 1595.78  5024.3 1598.57
  5038.5 1602.17  5080.9 1607.03  5109.2 1609.40  5123.3 1611.75  5137.5 1613.09
#Mann=5,-1,0
  4675.9    0.07       0  4801.3   0.035       0  4857.7    0.07       0
  4873.2    0.05       0  4877.2    0.07       0
Bank Sta=4873.2,4877.2
Exp/Cntr=0.3,0.1

Type RM Length L Ch R = 1,946,366,366,366
BEGIN DESCRIPTION:
Stream0080 2.0
END DESCRIPTION:
XS GIS Cut Line= 4
      1998992.64     13922089.45      1998266.35     13922236.90
      1998156.64     13922340.42      1998372.13     13922960.18
#Sta/Elev= 30
  4207.1 1621.60  4265.9 1619.42  4368.0 1618.31  4398.6 1615.45  4419.0 1615.65
  4500.6 1611.31  4582.4 1604.04  4634.4 1600.86  4880.8 1590.17  4913.7 1589.77
  4929.2 1586.41  4988.4 1581.61  4988.7 1581.11  4992.4 1581.61  5011.5 1583.17
  5025.6 1587.88  5046.7 1590.54  5075.0 1591.00  5098.7 1588.36  5202.6 1591.83
  5220.4 1590.27  5259.5 1590.04  5264.8 1591.75  5283.9 1590.99  5306.7 1593.48
  5321.7 1593.41  5365.9 1599.43  5499.9 1610.72  5643.8 1616.23  5755.2 1624.53
#Mann=9,-1,0
  4207.1    0.07       0  4582.4   0.035       0  4634.4    0.07       0
  4880.8     0.1       0  4988.4    0.05       0  4992.4     0.1       0
  5306.7    0.07       0  5365.9     0.1       0  5499.9    0.07       0
Bank Sta=4988.4,4992.4
Exp/Cntr=0.3,0.1

Type RM Length L Ch R = 1,580,442,442,442
BEGIN DESCRIPTION:
Stream0080 1.0
END DESCRIPTION:
XS GIS Cut Line= 4
      1998643.71     13921627.48      1998070.30     13921892.68
      1997970.45     13922110.68      1998239.38     13922940.75
#Sta/Elev= 30
  4270.5 1590.81  4418.6 1586.92  4574.2 1585.76  4686.7 1584.40  4824.9 1584.58
  4898.6 1582.47  4952.7 1580.63  4996.7 1574.24  4996.9 1573.74  5000.7 1574.24
  5090.7 1579.17  5119.2 1578.45  5210.2 1582.90  5314.8 1583.40  5396.9 1581.49
  5518.4 1583.07  5619.6 1586.26  5631.3 1584.26  5653.6 1584.41  5670.5 1584.50
  5754.0 1586.36  5786.0 1588.82  5791.3 1592.23  5802.9 1591.87  5818.0 1591.81
  5855.3 1595.71  5882.0 1595.57  5951.2 1606.71  5983.2 1615.03  6014.6 1616.02
#Mann=10,-1,0
  4270.5    0.07       0  4574.2   0.035       0  4686.7    0.07       0
  4898.6   0.035       0  4996.7   0.035       0  5000.7   0.035       0
  5518.4    0.07       0  5653.6   0.035       0  5670.5    0.07       0
  5802.9     0.1       0
Bank Sta=4996.7,5000.7
Exp/Cntr=0.3,0.1

Type RM Length L Ch R = 1,138,0,0,0
BEGIN DESCRIPTION:
Stream0080 0.0
END DESCRIPTION:
XS GIS Cut Line= 4
      1998150.04     13921592.57      1997661.08     13921880.69
      1997593.08     13922055.93      1997703.77     13922487.77
#Sta/Elev= 30
  4370.4 1578.69  4481.1 1577.65  4541.2 1577.75  4602.1 1577.70  4623.6 1578.84
  4654.8 1578.29  4756.4 1574.01  4820.8 1573.48  4895.0 1569.89  4929.4 1569.58
  4998.9 1566.56  5021.4 1563.51  5021.7 1563.01  5025.4 1563.51  5028.8 1567.31
  5039.1 1569.51  5048.0 1570.69  5053.3 1568.52  5060.5 1570.85  5094.6 1572.89
  5128.0 1574.43  5135.3 1576.10  5145.6 1576.51  5193.0 1575.43  5321.1 1576.78
  5365.3 1578.34  5424.4 1579.14  5496.6 1581.91  5514.2 1580.80  5571.7 1580.93
#Mann=9,-1,0
  4370.4   0.035       0  4481.1    0.07       0  4541.2   0.035       0
  4929.4    0.07       0  5021.4    0.05       0  5025.4    0.07       0
  5094.6   0.035       0  5365.3    0.07       0  5424.4   0.035       0
Bank Sta=5021.4,5025.4
Exp/Cntr=0.3,0.1

Chan Stop Cuts=-1