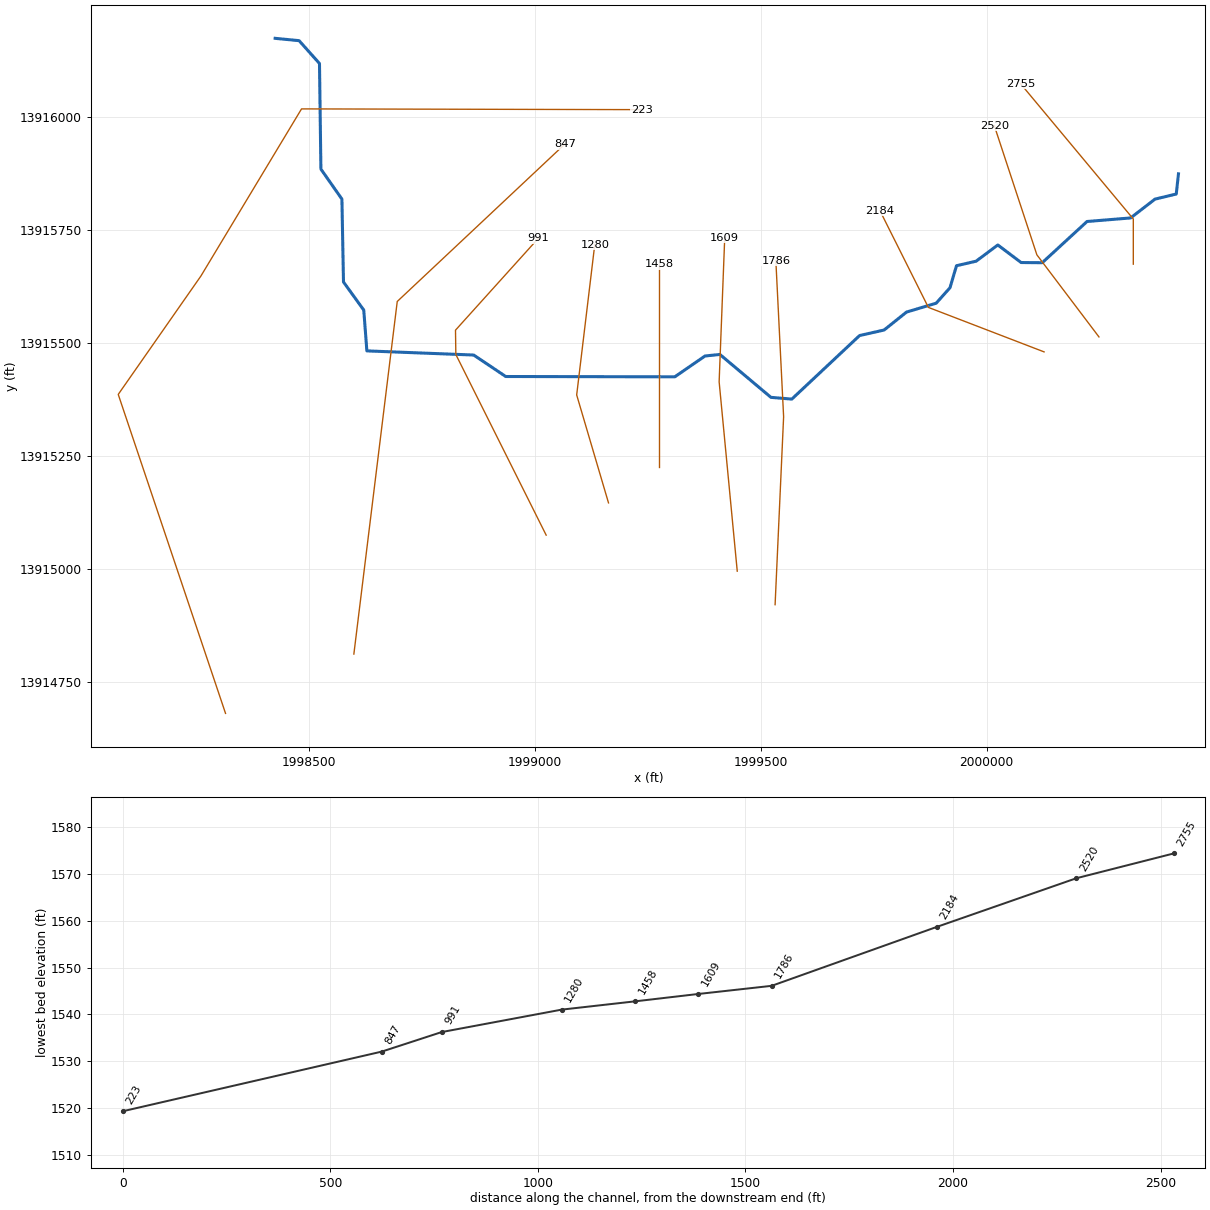
--- Stream0081.prj (project) ---

Proj Title=Stream0081 Base Level Engineering
Current Plan=p01
Default Exp/Contr=0.3,0.1
English Units
Geom File=g01
Flow File=f01
Plan File=p01
Y Axis Title=Elevation
X Axis Title(PF)=Main Channel Distance
X Axis Title(XS)=Station
BEGIN DESCRIPTION:
Stream0081
END DESCRIPTION:
DSS Export Rating Curves= 0
DSS Export Rating Curve Sorted= 0
DSS Export Volume Flow Curves= 0
DXF OffsetX= 0
DXF OffsetY= 0
DXF ScaleX= 1
DXF ScaleY= 10

--- Stream0081.p01 (plan) ---

Plan Title=Multiple Run
Short Identifier=Multiple
Geom File=g01
Flow File=f01
Subcritical Flow
K Sum by GR= 0
Std Step Tol= 0.01
Critical Tol= 0.01
Num of Std Step Trials= 20
Max Error Tol= 0.3
Flow Tol Ratio= 0.001
Split Flow NTrial= 30
Split Flow Tol= 0.02
Split Flow Ratio= 0.02
Log Output Level= 0
Friction Slope Method= 1
Unsteady Friction Slope Method= 2
Unsteady Bridges Friction Slope Method= 1
Parabolic Critical Depth
Global Vel Dist=  1 , 1 , 1
Global Log Level= 0
CheckData=True
Encroach Param= -1, 0, 0, 0
BEGIN DESCRIPTION:
Multiple Run
END DESCRIPTION:

--- Stream0081.f01 (steady flow) ---

Flow Title=Multiple
Program Version=4.10
Number of Profiles= 7
Profile Names=10-year,25-year,50-year,1pct_min,100-year,1pct_plu,500-year
River Rch & RM=Stream0081,Reach-1         ,2755
     396     644     873     578    1153    2301    1985
River Rch & RM=Stream0081,Reach-1         ,1786
     715    1210    1683    1140    2274    4537    4110
Boundary for River Rch & Prof#=Stream0081,Reach-1         , 1
Up Type= 0
Dn Type= 3
Dn Slope=0.01
Boundary for River Rch & Prof#=Stream0081,Reach-1         , 2
Up Type= 0
Dn Type= 3
Dn Slope=0.01
Boundary for River Rch & Prof#=Stream0081,Reach-1         , 3
Up Type= 0
Dn Type= 3
Dn Slope=0.01
Boundary for River Rch & Prof#=Stream0081,Reach-1         , 4
Up Type= 0
Dn Type= 3
Dn Slope=0.01
Boundary for River Rch & Prof#=Stream0081,Reach-1         , 5
Up Type= 0
Dn Type= 3
Dn Slope=0.01
Boundary for River Rch & Prof#=Stream0081,Reach-1         , 6
Up Type= 0
Dn Type= 3
Dn Slope=0.01
Boundary for River Rch & Prof#=Stream0081,Reach-1         , 7
Up Type= 0
Dn Type= 3
Dn Slope=0.01
DSS Import GetInterval= 0
DSS Import GetPeak= 0
DSS Import FillOption= 0

--- Stream0081.g01 (geometry) ---

Geom Title=Existing Conditions
Program Version=4.10

River Reach=Stream0081      ,Reach-1
Reach XY= 30
        2000425.       13915875.       2000420.1     13915830.28
        2000373.     13915818.96      2000319.06     13915777.31
      2000222.58     13915769.46      2000123.35     13915678.17
      2000076.65     13915678.58      2000024.97     13915717.45
      1999976.95     13915681.55      1999933.51     13915671.51
      1999919.11      13915622.8      1999888.54     13915588.54
      1999822.84     13915568.89      1999773.27     13915529.18
      1999718.92     13915516.91      1999568.94     13915376.23
      1999522.66     13915380.08      1999409.66     13915475.04
      1999376.75     13915471.66      1999309.79     13915425.54
       1998935.5     13915426.22      1998864.49     13915473.78
        1998628.     13915482.95      1998621.11     13915573.32
      1998576.22      13915635.5      1998572.74     13915819.06
      1998526.22      13915885.5      1998523.07     13916119.31
      1998477.95     13916169.87        1998425.       13916175.

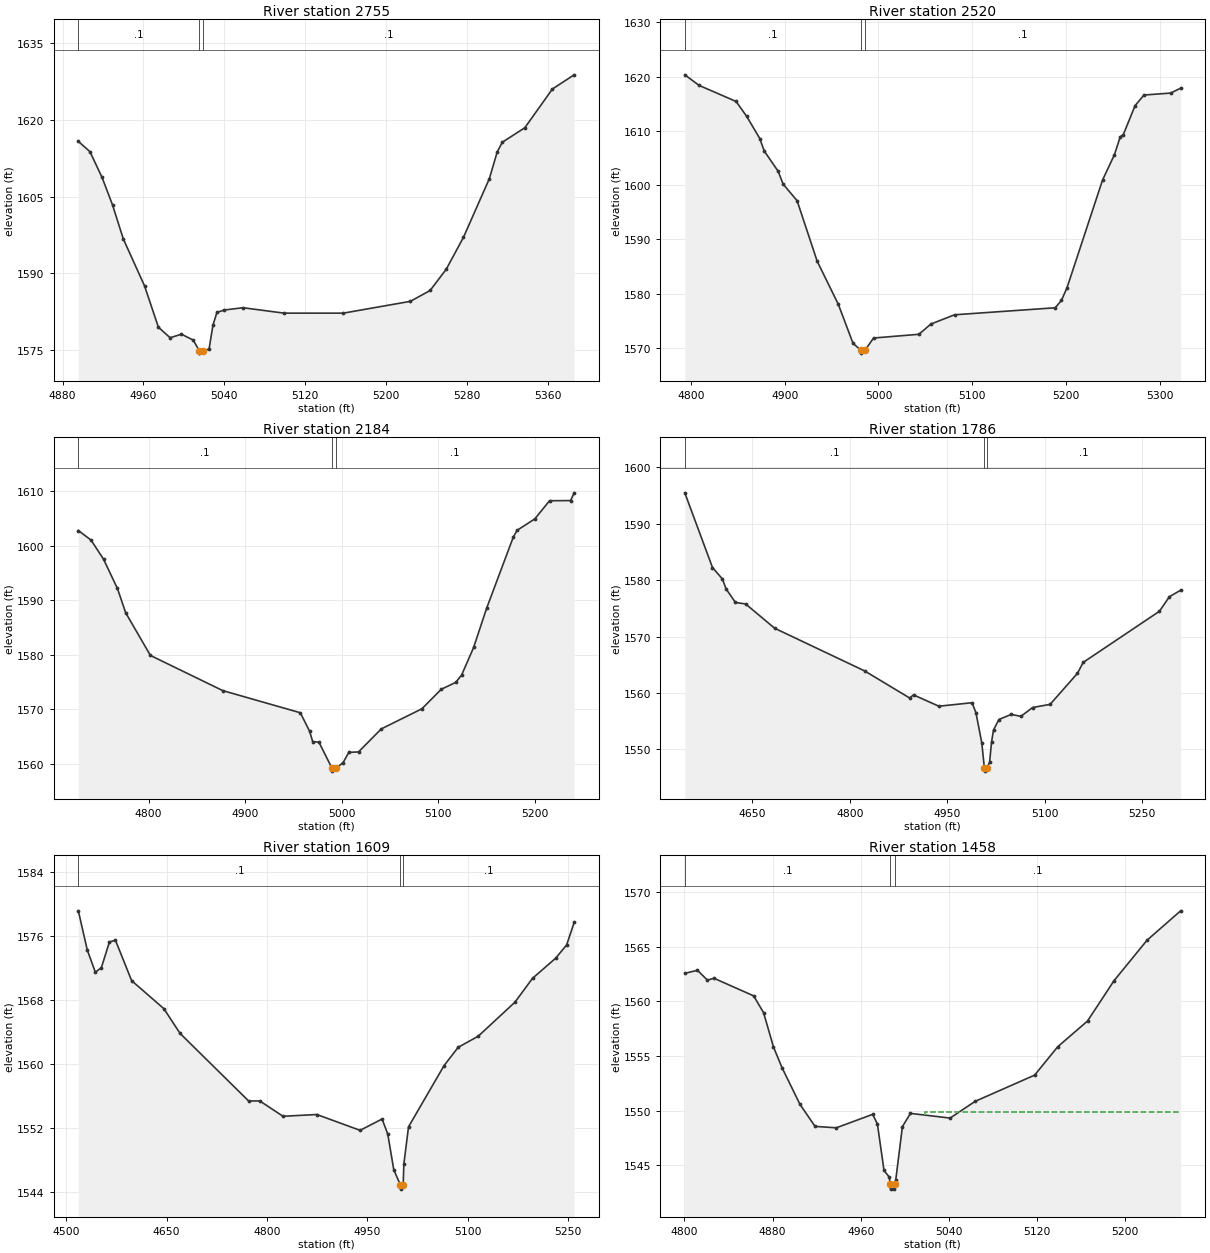
Type RM Length L Ch R = 1 ,2755    ,235,235,235
BEGIN DESCRIPTION:
Stream0081 5.0
END DESCRIPTION:
XS GIS Cut Line= 3
        2000325.     13915674.99        2000325.       13915775.
      2000075.01     13916074.98
#Sta/Elev= 30
  4895.6 1615.79  4907.1 1613.77  4919.1 1608.72  4929.4 1603.37  4940.1  1596.7
  4961.1 1587.52  4974.8 1579.44  4986.4 1577.38  4997.6 1578.07  5009.3 1576.92
  5015.1 1574.87  5015.3 1574.37  5019.1 1574.87  5024.9 1575.15  5028.8 1579.84
  5032.7 1582.33  5039.8  1582.8  5058.5 1583.25  5099.1 1582.19  5157.7 1582.19
  5224.1  1584.5  5243.6 1586.62  5259.6 1590.79  5276.6 1597.02  5302.2 1608.49
    5310 1613.73    5315 1615.61  5337.3 1618.45  5364.6 1626.03  5386.1  1628.8
#Mann= 3 ,-1 , 0
  4895.6      .1       0  5015.1     .05       0  5019.1      .1       0
Bank Sta=5015.1,5019.1
XS Rating Curve= 0 ,0
Exp/Cntr=0.3,0.1

Type RM Length L Ch R = 1 ,2520    ,336,336,336
BEGIN DESCRIPTION:
Stream0081 4.1
END DESCRIPTION:
XS GIS Cut Line= 3
      2000248.97     13915513.89      2000111.48     13915695.67
      2000017.23     13915981.62
#Sta/Elev= 30
  4793.4 1620.31  4808.8 1618.35  4848.1 1615.41  4859.4 1612.67  4873.4 1608.58
  4878.2 1606.27    4893 1602.55  4898.3 1600.19  4913.2 1597.14  4934.6 1586.01
  4957.2 1578.05  4972.9 1570.87  4981.5 1569.57  4981.7 1569.07  4985.5 1569.57
  4994.8 1571.85  5043.2 1572.54  5055.9 1574.42  5081.2 1576.13  5188.6 1577.42
  5195.2 1578.77  5201.2 1581.11  5239.1 1600.94  5251.7 1605.57    5258 1608.91
  5261.2 1609.28  5273.8 1614.64  5283.3 1616.59  5311.7 1616.95  5322.4 1617.85
#Mann= 3 ,-1 , 0
  4793.4      .1       0  4981.5     .05       0  4985.5      .1       0
Bank Sta=4981.5,4985.5
XS Rating Curve= 0 ,0
Exp/Cntr=0.3,0.1

Type RM Length L Ch R = 1 ,2184    ,398,398,398
BEGIN DESCRIPTION:
Stream0081 4.0
END DESCRIPTION:
XS GIS Cut Line= 3
      2000127.47     13915480.75      1999871.28     13915579.25
      1999764.07     13915793.34
#Sta/Elev= 30
  4727.2  1602.8  4740.4 1601.04  4753.3 1597.55  4767.7 1592.18  4776.3 1587.71
  4801.9  1579.9  4876.9 1573.45  4957.3 1569.39  4966.9    1566  4970.1 1564.11
  4976.6 1563.99  4990.2 1559.19  4990.5 1558.69  4994.2 1559.19  5001.7 1560.27
  5007.5 1562.13  5017.6 1562.21  5041.1 1566.42  5083.3 1570.12  5103.4  1573.7
  5118.3 1574.95  5124.5 1576.32  5136.9 1581.36  5150.3 1588.51  5178.1 1601.63
    5182 1602.84  5200.3 1604.93  5215.6 1608.26  5237.4 1608.29  5241.1 1609.71
#Mann= 3 ,-1 , 0
  4727.2      .1       0  4990.2     .05       0  4994.2      .1       0
Bank Sta=4990.2,4994.2
XS Rating Curve= 0 ,0
Exp/Cntr=0.3,0.1

Type RM Length L Ch R = 1 ,1786    ,177,177,177
BEGIN DESCRIPTION:
Stream0081 3.0
END DESCRIPTION:
XS GIS Cut Line= 3
      1999531.87     13914920.99      1999550.74      13915337.2
      1999533.52     13915683.03
#Sta/Elev= 30
  4546.2  1595.5  4588.8 1582.24    4604 1580.22  4609.7 1578.45  4624.1 1576.04
  4639.8 1575.78  4684.4 1571.47    4823 1563.89  4892.1 1559.09  4898.1 1559.64
  4937.1 1557.63  4988.2 1558.25  4994.2 1556.47  5003.2 1551.09  5007.2 1546.61
  5007.4 1546.11  5011.2 1546.61  5015.2 1547.71  5018.2 1551.29  5021.2 1553.41
  5029.5 1555.27  5048.5 1556.18  5063.3 1555.83  5081.3  1557.4  5108.3 1557.96
  5150.4 1563.47  5159.1  1565.4  5276.5 1574.48  5291.9 1577.08  5309.1 1578.21
#Mann= 3 ,-1 , 0
  4546.2      .1       0  5007.2     .05       0  5011.2      .1       0
Bank Sta=5007.2,5011.2
XS Rating Curve= 0 ,0
Exp/Cntr=0.3,0.1

Type RM Length L Ch R = 1 ,1609    ,151,151,151
BEGIN DESCRIPTION:
Mapping XS 62947a7e
END DESCRIPTION:
XS GIS Cut Line= 3
      1999448.07     13914995.21      1999407.97      13915414.6
      1999420.35     13915733.66
#Sta/Elev= 30
  4518.3 1579.17  4531.6 1574.29  4543.7 1571.49  4552.7 1572.06  4564.8 1575.29
  4573.8 1575.48  4597.9 1570.44    4646 1566.94  4670.3 1563.84  4772.7 1555.39
  4789.3  1555.4    4824 1553.48  4874.6  1553.7  4939.2 1551.72    4972 1553.14
  4980.5 1551.25  4989.5 1546.78  4999.5 1544.87  4999.8 1544.37  5003.5 1544.87
  5004.5  1547.5  5011.5 1552.16  5064.6 1559.82  5085.6  1562.1  5115.6 1563.49
  5170.5 1567.75  5196.7 1570.73  5231.2 1573.24  5247.7 1574.91  5258.9 1577.72
#Mann= 3 ,-1 , 0
  4518.3      .1       0  4999.5     .05       0  5003.5      .1       0
#XS Ineff= 2 , 0
         4971.53 1553.01
Permanent Ineff=
       F       F
Bank Sta=4999.5,5003.5
XS Rating Curve= 0 ,0
Exp/Cntr=0.3,0.1

Type RM Length L Ch R = 1 ,1458    ,178,178,178
BEGIN DESCRIPTION:
Stream0081 2.0
END DESCRIPTION:
XS GIS Cut Line= 3
        1999275.     13915225.01        1999275.       13915425.
        1999275.     13915675.01
#Sta/Elev= 30
  4800.4 1562.55  4811.9 1562.83  4820.9 1561.93  4826.9  1562.1  4862.9 1560.49
  4871.9 1558.95  4880.9 1555.81  4888.6 1553.93  4904.9 1550.57  4918.6 1548.55
  4937.9 1548.42  4970.9 1549.65  4975.2 1548.77  4981.2 1544.52  4985.9 1543.92
  4986.9 1543.31  4987.1 1542.81  4990.6 1542.81  4990.9 1543.31  4991.9 1543.68
  4997.9 1548.53  5005.2 1549.74  5041.2 1549.31  5063.9 1550.84  5117.9 1553.24
  5138.9 1555.84  5165.9 1558.19  5189.9 1561.87  5219.9 1565.58  5250.4 1568.27
#Mann= 3 ,-1 , 0
  4800.4      .1       0  4986.9     .05       0  4990.9      .1       0
#XS Ineff= 2 , 0
                         5018.28         1549.88
Permanent Ineff=
       F       F
Bank Sta=4986.9,4990.9
XS Rating Curve= 0 ,0
Exp/Cntr=0.3,0.1

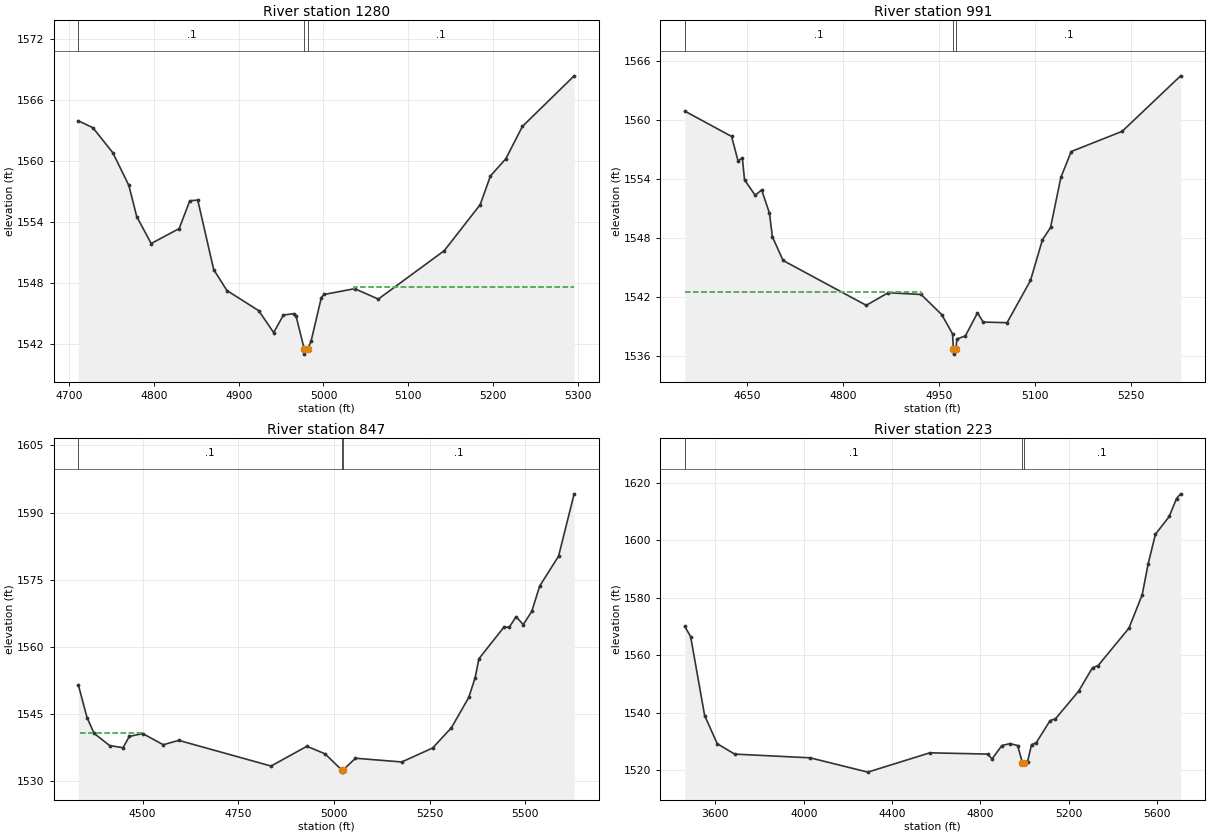
Type RM Length L Ch R = 1 ,1280    ,289,289,289
BEGIN DESCRIPTION:
Mapping XS 6b2ab635
END DESCRIPTION:
XS GIS Cut Line= 3
      1999163.01     13915146.44      1999092.55     13915385.38
       1999132.6     13915718.47
#Sta/Elev= 30
    4711 1563.96  4728.2 1563.28  4751.7 1560.82  4770.5 1557.62  4779.9 1554.54
  4796.9  1551.9  4829.9 1553.37  4842.4  1556.1  4851.8 1556.17  4870.6 1549.34
  4886.2 1547.28  4923.7  1545.3  4941.3 1543.15  4952.8 1544.87  4964.9 1545.01
  4967.6  1544.8  4977.4 1541.53  4977.6 1541.03  4981.4 1541.53  4985.4  1542.3
  4997.5 1546.58  5000.5 1546.89  5036.8 1547.46  5064.7 1546.44  5142.5  1551.2
  5184.8 1555.72  5196.9 1558.54  5215.1 1560.24  5234.6 1563.41  5295.6 1568.38
#Mann= 3 ,-1 , 0
    4711      .1       0  4977.4     .05       0  4981.4      .1       0
#XS Ineff= 2 , 0
                         5036.26         1547.66
Permanent Ineff=
       F       F
Bank Sta=4977.4,4981.4
XS Rating Curve= 0 ,0
Exp/Cntr=0.3,0.1

Type RM Length L Ch R = 1 ,991     ,144,144,144
BEGIN DESCRIPTION:
Stream0081 1.0
END DESCRIPTION:
XS GIS Cut Line= 4
        1999025.     13915074.99        1998825.       13915475.
      1998824.23     13915528.86      1999007.94     13915732.58
#Sta/Elev= 30
  4552.4 1560.89  4625.6 1558.32  4635.7 1555.83  4642.4 1556.16  4645.8 1553.92
  4662.5 1552.35  4672.6  1552.9  4684.8 1550.54  4689.4 1548.14  4706.1 1545.74
  4836.2 1541.19  4870.5 1542.47    4922 1542.29  4954.3 1540.24  4971.1  1538.3
  4972.5 1536.74  4972.7 1536.24  4976.5 1536.74  4977.8 1537.77  4991.2 1538.09
  5010.1 1540.42  5019.1 1539.49  5056.4 1539.43    5093 1543.71  5111.6 1547.82
  5124.4 1549.09  5140.5 1554.16  5156.7 1556.79  5236.4 1558.84  5327.8 1564.47
#Mann= 3 ,-1 , 0
  4552.4      .1       0  4972.5     .05       0  4976.5      .1       0
#XS Ineff= 2 , 0
         4921.48 1542.54
Permanent Ineff=
       F       F
Bank Sta=4972.5,4976.5
XS Rating Curve= 0 ,0
Exp/Cntr=0.3,0.1

Type RM Length L Ch R = 1 ,847     ,624,624,624
BEGIN DESCRIPTION:
Mapping XS 245bace1
END DESCRIPTION:
XS GIS Cut Line= 3
       1998599.2     13914811.67      1998695.25     13915592.36
       1999066.4     13915940.86
#Sta/Elev= 30
  4332.2 1551.55  4354.9 1544.27  4373.3 1540.74  4414.1    1538  4449.1 1537.53
  4465.3 1540.04  4500.3  1540.7  4554.1 1538.19  4594.5 1539.17  4835.8 1533.44
  4929.5 1537.85  4976.7 1536.17  5020.4 1532.58  5020.7 1532.08  5024.4 1532.58
  5056.4 1535.18  5177.4 1534.35  5257.9 1537.46  5307.3    1542  5352.6 1548.78
  5369.1 1553.13    5379 1557.38  5443.9 1564.39  5458.8 1564.47  5476.1 1566.78
  5494.9 1565.01  5517.2 1567.97  5537.8  1573.6  5587.2 1580.29  5627.9 1594.19
#Mann= 3 ,-1 , 0
  4332.2      .1       0  5020.4     .05       0  5024.4      .1       0
#XS Ineff= 3 ,-1
  4332.2 4335.86 1537.68 4335.86  4497.3  1540.9  4497.3 4933.67 1537.68
Permanent Ineff=
       F       F       F
Bank Sta=5020.4,5024.4
XS Rating Curve= 0 ,0
Exp/Cntr=0.3,0.1

Type RM Length L Ch R = 1 ,223     ,0,0,0
BEGIN DESCRIPTION:
Stream0081 0.0
END DESCRIPTION:
XS GIS Cut Line= 5
      1998315.04     13914680.36      1998077.49     13915386.61
      1998260.66     13915648.92      1998483.32     13916018.76
      1999236.77     13916017.12
#Sta/Elev= 30
  3461.5 1570.04    3488 1566.48  3551.3 1539.05  3608.3 1529.24  3687.4 1525.62
    4029 1524.33  4290.3 1519.35  4571.2 1526.07  4833.1 1525.63  4852.7 1523.93
    4897 1528.59  4933.6 1529.28  4968.6  1528.6 4990.21 1522.63  4995.6 1522.56
  5013.6 1523.03  5031.6 1528.93  5052.6 1529.55  5115.6  1537.3  5139.6 1537.89
  5244.6  1547.5  5307.6 1555.69  5333.2 1556.44  5472.6 1569.45  5532.6 1581.07
  5559.6 1591.85  5592.6 1602.12  5654.9  1608.3    5688 1614.55  5706.6 1616.18
#Mann= 3 ,-1 , 0
  3461.5      .1       0 4990.21     .05       0  4995.6      .1       0
#Block Obstruct= 2 , 0
         4576.42 1525.39
Bank Sta=4990.21,4995.6
XS Rating Curve= 0 ,0
Exp/Cntr=0.3,0.1

Chan Stop Cuts=-1
Use User Specified Reach Order=0
Composite Channel Slope=5