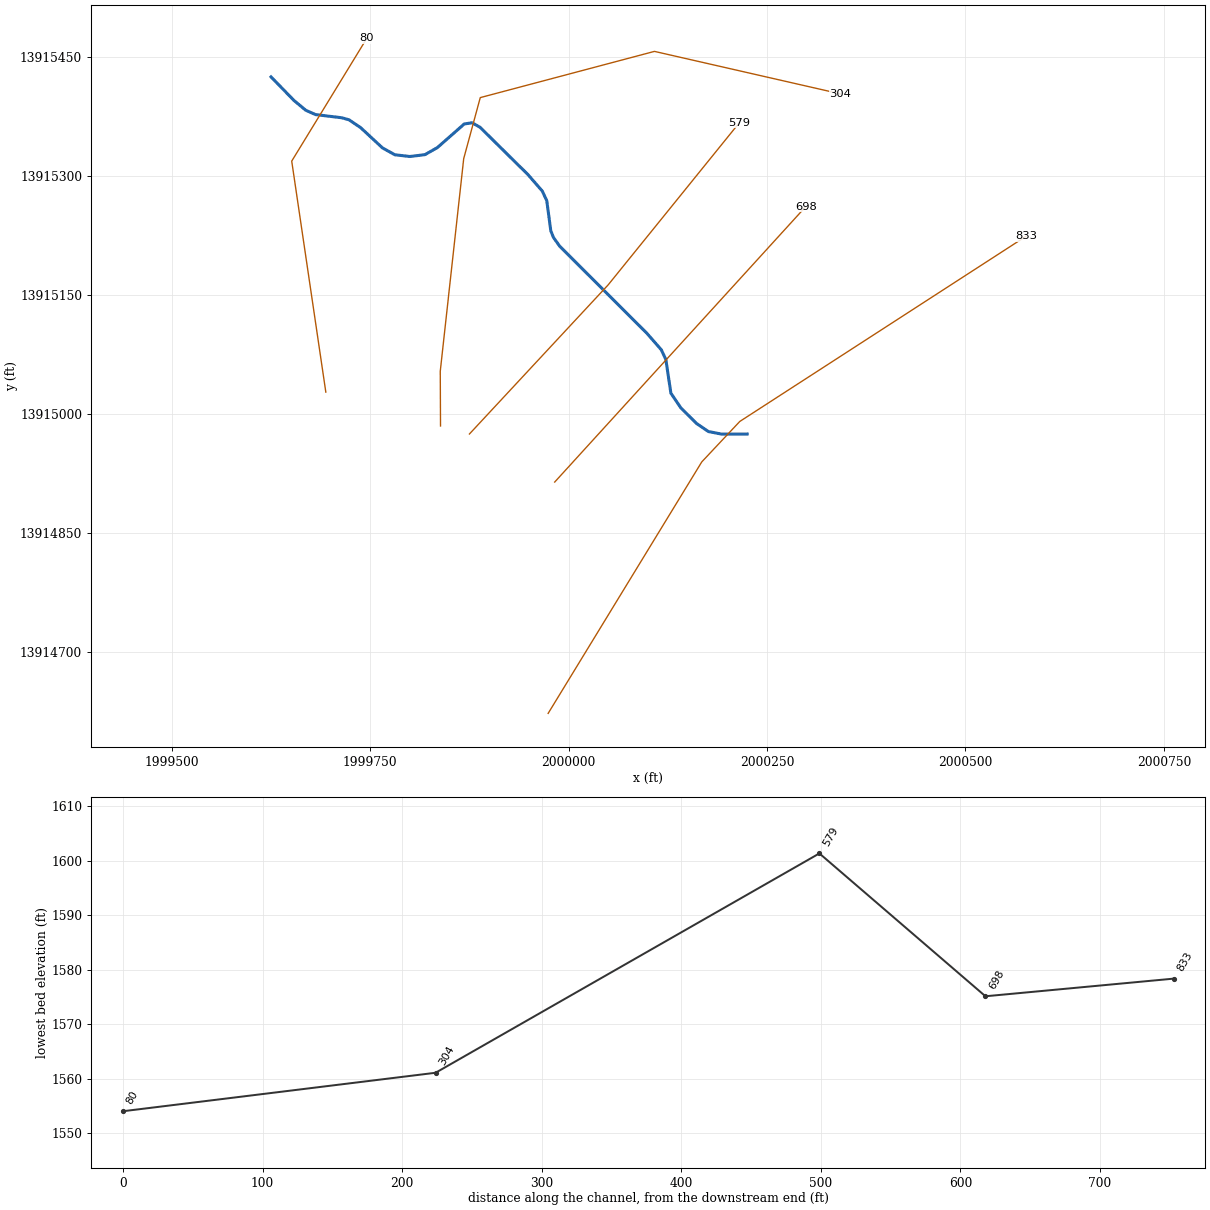
--- Stream0082.prj (project) ---

Proj Title=Stream0082 Base Level Engineering
Current Plan=p01
Default Exp/Contr=0.3,0.1
English Units
Geom File=g01
Flow File=f01
Plan File=p01
BEGIN DESCRIPTION:
Stream0082
END DESCRIPTION:

--- Stream0082.p01 (plan) ---

Plan Title=Multiple Run
Short Identifier=Multiple
Geom File=g01
Flow File=f01
Subcritical Flow
K Sum by GR= 0
Std Step Tol= 0.01
Critical Tol= 0.01
Num of Std Step Trials= 20
Max Error Tol= 0.3
Flow Tol Ratio= 0.001
Split Flow NTrial= 30
Split Flow Tol= 0.02
Split Flow Ratio= 0.02
Log Output Level= 0
Friction Slope Method= 1
Unsteady Friction Slope Method= 2
Unsteady Bridges Friction Slope Method= 1
Parabolic Critical Depth
Global Vel Dist=  1 , 1 , 1
Global Log Level= 0
CheckData=True
Encroach Param= -1, 0, 0, 0
BEGIN DESCRIPTION:
Multiple Run
END DESCRIPTION:

--- Stream0082.f01 (steady flow) ---

Flow Title=Multiple
Number of Profiles=7
Profile Names=10-year,25-year,50-year,1pct_min,100-year,1pct_plu,500-year
River Rch & RM= Stream0082,Reach-1,833
     246     386     509     329     657    1310    1075
Boundary for River Rch & Prof#=Stream0082,Reach-1,1
Up Type=0
Dn Type=3
Dn Slope=0.005
Boundary for River Rch & Prof#=Stream0082,Reach-1,2
Up Type=0
Dn Type=3
Dn Slope=0.005
Boundary for River Rch & Prof#=Stream0082,Reach-1,3
Up Type=0
Dn Type=3
Dn Slope=0.005
Boundary for River Rch & Prof#=Stream0082,Reach-1,4
Up Type=0
Dn Type=3
Dn Slope=0.005
Boundary for River Rch & Prof#=Stream0082,Reach-1,5
Up Type=0
Dn Type=3
Dn Slope=0.005
Boundary for River Rch & Prof#=Stream0082,Reach-1,6
Up Type=0
Dn Type=3
Dn Slope=0.005
Boundary for River Rch & Prof#=Stream0082,Reach-1,7
Up Type=0
Dn Type=3
Dn Slope=0.005

--- Stream0082.g01 (geometry) ---

Geom Title=Existing Conditions

River Reach=Stream0082,Reach-1
Reach XY= 30
      2000225.00     13914975.00      2000192.95     13914974.85
      2000176.03     13914978.14      2000161.22     13914988.27
      2000141.39     13915007.97      2000128.86     13915026.46
      2000122.49     13915068.94      2000116.85     13915081.04
      2000098.70     13915101.82      1999988.63     13915211.79
      1999980.86     13915222.71      1999977.54     13915231.05
      1999972.47     13915268.97      1999966.84     13915281.09
      1999948.70     13915301.95      1999888.40     13915361.47
      1999878.42     13915367.19      1999868.46     13915365.67
      1999834.68     13915335.94      1999818.97     13915327.02
      1999800.04     13915324.68      1999781.12     13915326.83
      1999765.45     13915335.50      1999738.08     13915360.91
      1999723.33     13915370.89      1999714.38     13915373.46
      1999681.04     13915377.50      1999668.85     13915382.91
      1999654.08     13915395.14      1999625.00     13915425.00

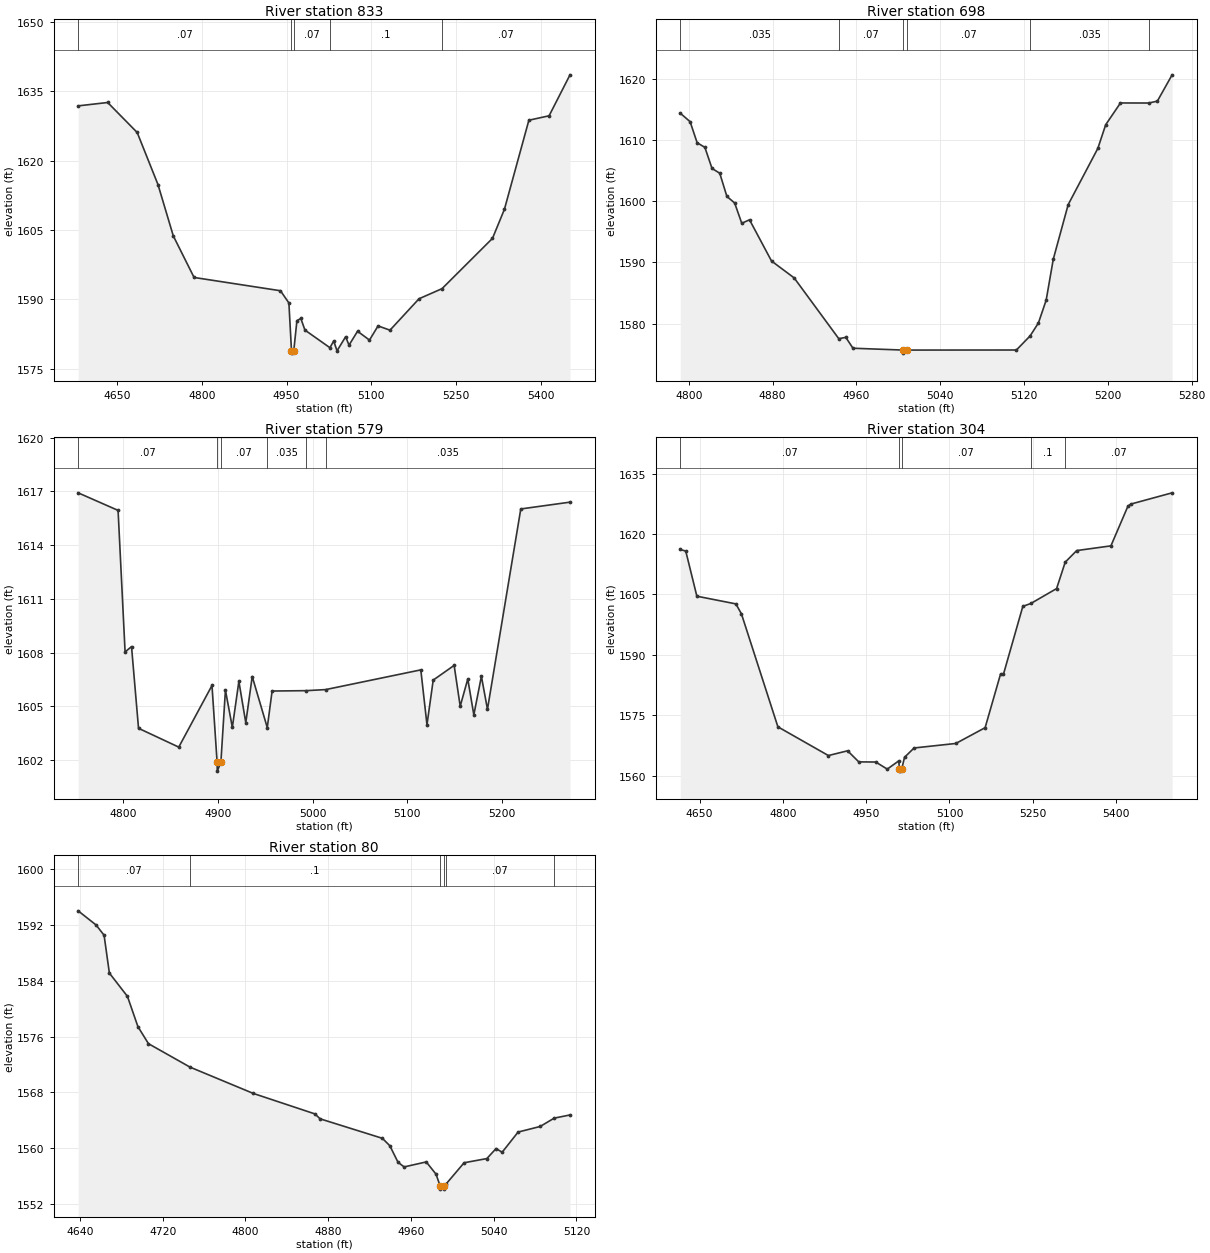
Type RM Length L Ch R = 1,833,135,135,135
BEGIN DESCRIPTION:
Stream0082 2.0
END DESCRIPTION:
XS GIS Cut Line= 4
      1999974.21     13914622.98      2000167.78     13914939.86
      2000215.66     13914990.80      2000576.09     13915223.96
#Sta/Elev= 30
  4581.1 1631.84  4633.4 1632.57  4685.6 1626.09  4722.4 1614.84  4749.5 1603.75
  4786.3 1594.76  4939.2 1591.89  4954.1 1589.25  4958.7 1578.91  4958.9 1578.41
  4962.7 1578.91  4968.3 1585.42  4975.2 1585.90  4982.5 1583.39  5026.7 1579.58
  5033.4 1581.03  5039.3 1578.91  5054.5 1581.95  5060.5 1580.13  5075.6 1583.14
  5096.7 1581.23  5111.9 1584.29  5133.0 1583.37  5184.4 1590.16  5225.1 1592.34
  5314.4 1603.21  5335.5 1609.48  5378.8 1628.74  5414.6 1629.70  5451.6 1638.55
#Mann=5,-1,0
  4581.1    0.07       0  4958.7    0.05       0  4962.7    0.07       0
  5026.7     0.1       0  5225.1    0.07       0
Bank Sta=4958.7,4962.7
Exp/Cntr=0.3,0.1

Type RM Length L Ch R = 1,698,119,119,119
BEGIN DESCRIPTION:
Mapping XS e4a35377
END DESCRIPTION:
XS GIS Cut Line= 2
      1999982.45     13914914.45      2000298.65     13915261.38
#Sta/Elev= 30
  4791.9 1614.40  4801.3 1613.01  4808.0 1609.57  4815.4 1608.81  4822.2 1605.37
  4829.6 1604.58  4836.4 1600.79  4843.8 1599.72  4850.6 1596.40  4858.0 1596.97
  4879.0 1590.23  4900.6 1587.47  4943.2 1577.53  4949.9 1577.75  4956.7 1575.97
  5004.6 1575.67  5004.9 1575.17  5008.6 1575.67  5112.7 1575.68  5125.8 1577.99
  5133.7 1580.10  5141.1 1583.83  5147.9 1590.54  5162.1 1599.45  5190.4 1608.64
  5197.9 1612.51  5212.0 1616.07  5239.0 1616.06  5247.2 1616.37  5261.3 1620.67
#Mann=6,-1,0
  4791.9   0.035       0  4943.2    0.07       0  5004.6    0.05       0
  5008.6    0.07       0  5125.8   0.035       0  5239.0    0.07       0
Bank Sta=5004.6,5008.6
Exp/Cntr=0.3,0.1

Type RM Length L Ch R = 1,579,275,275,275
BEGIN DESCRIPTION:
Stream0082 1.0
END DESCRIPTION:
XS GIS Cut Line= 3
      1999875.00     13914975.00      2000049.84     13915162.94
      2000215.19     13915367.35
#Sta/Elev= 30
  4752.4 1616.92  4794.6 1615.94  4802.0 1608.04  4808.8 1608.34  4816.2 1603.78
  4858.7 1602.73  4893.8 1606.17  4899.2 1601.89  4899.4 1601.39  4903.2 1601.89
  4908.0 1605.91  4915.3 1603.83  4922.2 1606.40  4929.5 1604.09  4936.3 1606.67
  4952.2 1603.82  4957.3 1605.86  4993.2 1605.88  5013.9 1605.94  5114.4 1607.04
  5120.9 1603.98  5127.5 1606.47  5149.6 1607.29  5156.0 1605.01  5164.0 1606.53
  5170.4 1604.53  5178.4 1606.68  5184.8 1604.84  5220.0 1616.02  5272.0 1616.40
#Mann=6,-1,0
  4752.4    0.07       0  4899.2    0.05       0  4903.2    0.07       0
  4952.2   0.035       0  4993.2    0.07       0  5013.9   0.035       0
Bank Sta=4899.2,4903.2
Exp/Cntr=0.3,0.1

Type RM Length L Ch R = 1,304,224,224,224
BEGIN DESCRIPTION:
Stream0082 0.0
END DESCRIPTION:
XS GIS Cut Line= 6
      1999838.58     13914985.13      1999838.25     13915054.06
      1999867.79     13915321.97      1999888.66     13915398.89
      2000108.15     13915457.13      2000342.47     13915403.61
#Sta/Elev= 30
  4615.3 1616.17  4625.2 1615.77  4645.2 1604.57  4715.4 1602.66  4725.4 1600.21
  4791.1 1572.13  4882.0 1565.00  4916.6 1566.18  4936.7 1563.43  4967.3 1563.39
  4988.0 1561.63  5008.7 1563.67  5010.0 1561.63  5010.3 1561.13  5014.0 1561.63
  5019.1 1564.56  5036.3 1566.88  5111.5 1568.00  5164.2 1571.92  5191.9 1585.20
  5197.1 1585.13  5232.1 1602.05  5246.5 1602.76  5292.9 1606.46  5308.4 1613.02
  5329.1 1615.90  5390.7 1617.07  5421.4 1626.95  5426.9 1627.46  5500.9 1630.24
#Mann=5,-1,0
  4615.3    0.07       0  5010.0    0.05       0  5014.0    0.07       0
  5246.5     0.1       0  5308.4    0.07       0
Bank Sta=5010,5014
Exp/Cntr=0.3,0.1

Type RM Length L Ch R = 1,80,0,0,0
BEGIN DESCRIPTION:
Stream0082 0.1
END DESCRIPTION:
XS GIS Cut Line= 3
      1999694.05     13915027.78      1999651.08     13915318.87
      1999745.70     13915473.58
#Sta/Elev= 30
  4638.2 1594.06  4655.6 1592.02  4663.3 1590.55  4668.4 1585.12  4685.9 1581.76
  4696.0 1577.42  4706.2 1574.97  4746.4 1571.60  4807.6 1567.82  4867.1 1564.88
  4872.2 1564.17  4932.4 1561.37  4939.6 1560.30  4947.5 1557.93  4953.4 1557.26
  4974.8 1557.98  4984.3 1556.21  4988.1 1554.57  4988.4 1554.07  4991.9 1554.07
  4992.1 1554.57  4994.1 1554.83  5011.4 1557.86  5033.4 1558.46  5042.3 1559.90
  5048.2 1559.37  5063.6 1562.27  5084.9 1563.07  5098.5 1564.27  5113.8 1564.73
#Mann=6,-1,0
  4638.2    0.07       0  4746.4     0.1       0  4988.1    0.05       0
  4992.1     0.1       0  4994.1    0.07       0  5098.5   0.035       0
Bank Sta=4988.1,4992.1
Exp/Cntr=0.3,0.1

Chan Stop Cuts=-1