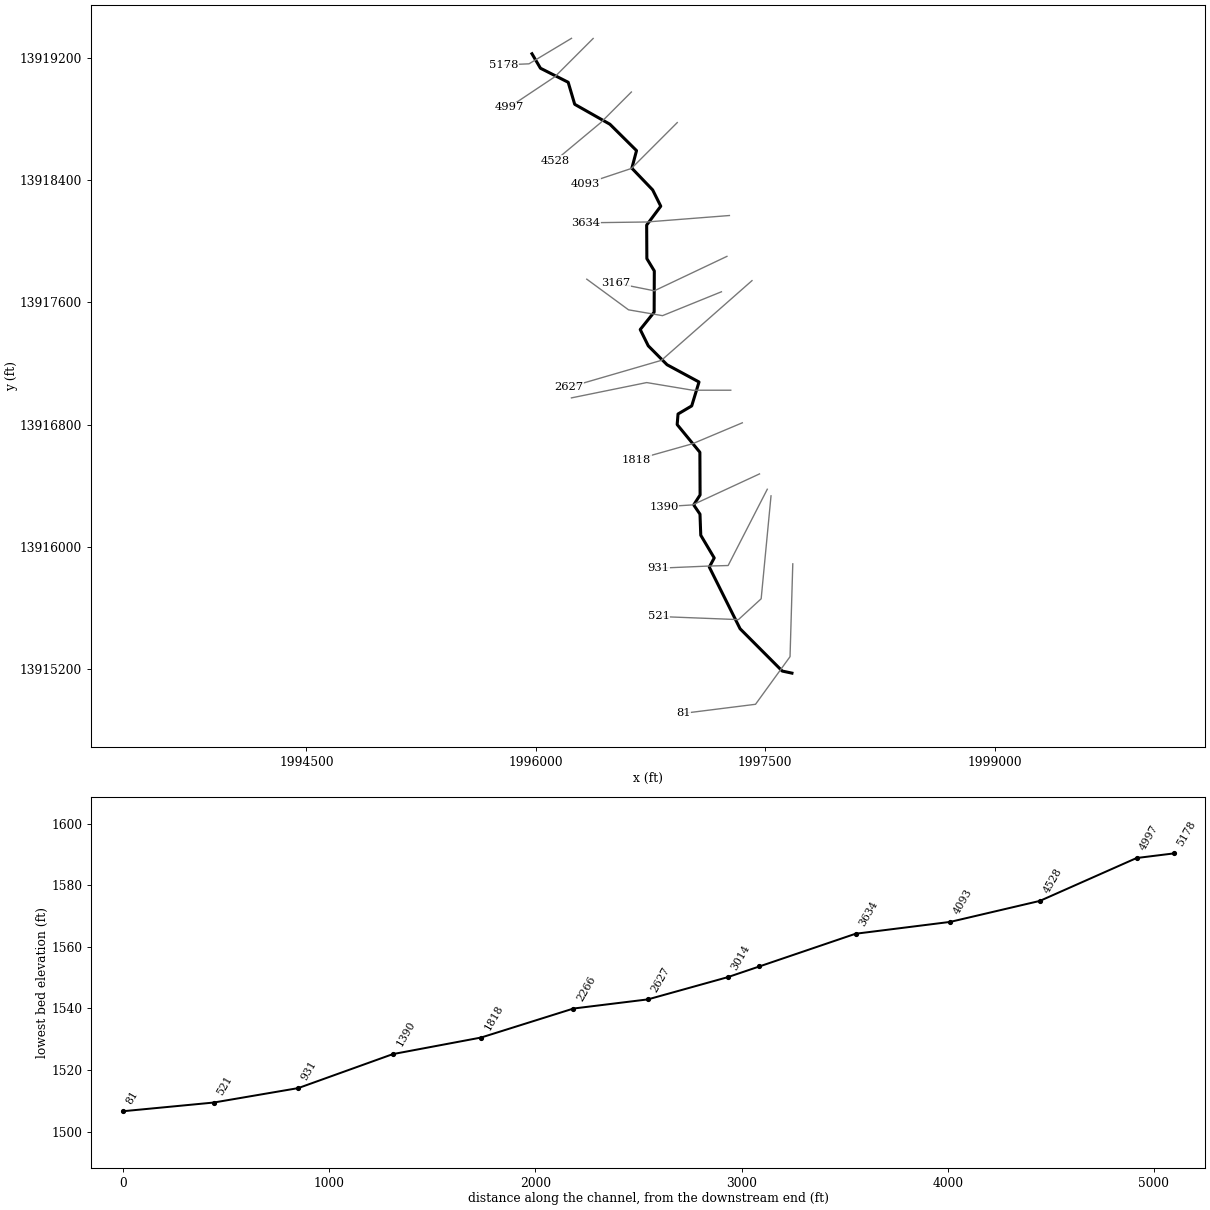
--- Stream0083.prj (project) ---

Proj Title=Stream0083 Base Level Engineering
Current Plan=p01
Default Exp/Contr=0.3,0.1
English Units
Geom File=g01
Flow File=f01
Plan File=p01
Y Axis Title=Elevation
X Axis Title(PF)=Main Channel Distance
X Axis Title(XS)=Station
BEGIN DESCRIPTION:
Stream0083
END DESCRIPTION:
DSS Export Rating Curves= 0
DSS Export Rating Curve Sorted= 0
DSS Export Volume Flow Curves= 0
DXF OffsetX= 0
DXF OffsetY= 0
DXF ScaleX= 1
DXF ScaleY= 10

--- Stream0083.p01 (plan) ---

Plan Title=Multiple Run
Short Identifier=Multiple
Geom File=g01
Flow File=f01
Subcritical Flow
K Sum by GR= 0
Std Step Tol= 0.01
Critical Tol= 0.01
Num of Std Step Trials= 20
Max Error Tol= 0.3
Flow Tol Ratio= 0.001
Split Flow NTrial= 30
Split Flow Tol= 0.02
Split Flow Ratio= 0.02
Log Output Level= 0
Friction Slope Method= 1
Unsteady Friction Slope Method= 2
Unsteady Bridges Friction Slope Method= 1
Parabolic Critical Depth
Global Vel Dist=  1 , 1 , 1
Global Log Level= 0
CheckData=True
Encroach Param= -1, 0, 0, 0
BEGIN DESCRIPTION:
Multiple Run
END DESCRIPTION:

--- Stream0083.f01 (steady flow) ---

Flow Title=Multiple
Number of Profiles=7
Profile Names=10-year,25-year,50-year,1pct_min,100-year,1pct_plu,500-year
River Rch & RM= Stream0083,Reach-1,5178
     794    1356    1896    1290    2573    5134    4696
River Rch & RM= Stream0083,Reach-1,2627
    1048    1809    2546    1741    3475    6933    6411
Boundary for River Rch & Prof#=Stream0083,Reach-1,1
Up Type=0
Dn Type=3
Dn Slope=0.005
Boundary for River Rch & Prof#=Stream0083,Reach-1,2
Up Type=0
Dn Type=3
Dn Slope=0.005
Boundary for River Rch & Prof#=Stream0083,Reach-1,3
Up Type=0
Dn Type=3
Dn Slope=0.005
Boundary for River Rch & Prof#=Stream0083,Reach-1,4
Up Type=0
Dn Type=3
Dn Slope=0.005
Boundary for River Rch & Prof#=Stream0083,Reach-1,5
Up Type=0
Dn Type=3
Dn Slope=0.005
Boundary for River Rch & Prof#=Stream0083,Reach-1,6
Up Type=0
Dn Type=3
Dn Slope=0.005
Boundary for River Rch & Prof#=Stream0083,Reach-1,7
Up Type=0
Dn Type=3
Dn Slope=0.005

--- Stream0083.g01 (geometry) ---

Geom Title=Existing Conditions
Program Version=4.10

River Reach=Stream0083      ,Reach-1
Reach XY= 30
        1995975.       13919225.      1996030.42     13919130.48
      1996211.74     13919038.66      1996254.43     13918894.59
      1996484.68     13918764.22       1996658.7      13918591.7
      1996628.16     13918476.65      1996764.25     13918334.68
      1996817.16     13918228.23      1996724.97     13918105.02
      1996726.22      13917885.5      1996774.93     13917804.97
      1996773.94     13917535.43      1996682.82     13917421.76
      1996735.45     13917315.21      1996858.29     13917191.56
      1997067.31     13917078.67      1997019.54     13916922.34
      1996930.13     13916869.51      1996924.42     13916800.15
      1997072.94     13916619.15      1997074.34     13916340.16
      1997032.56       13916275.       1997073.6     13916214.56
      1997078.76     13916076.56      1997166.76     13915928.23
      1997134.58     13915868.45      1997335.76     13915465.32
      1997611.73     13915188.47        1997675.       13915175.

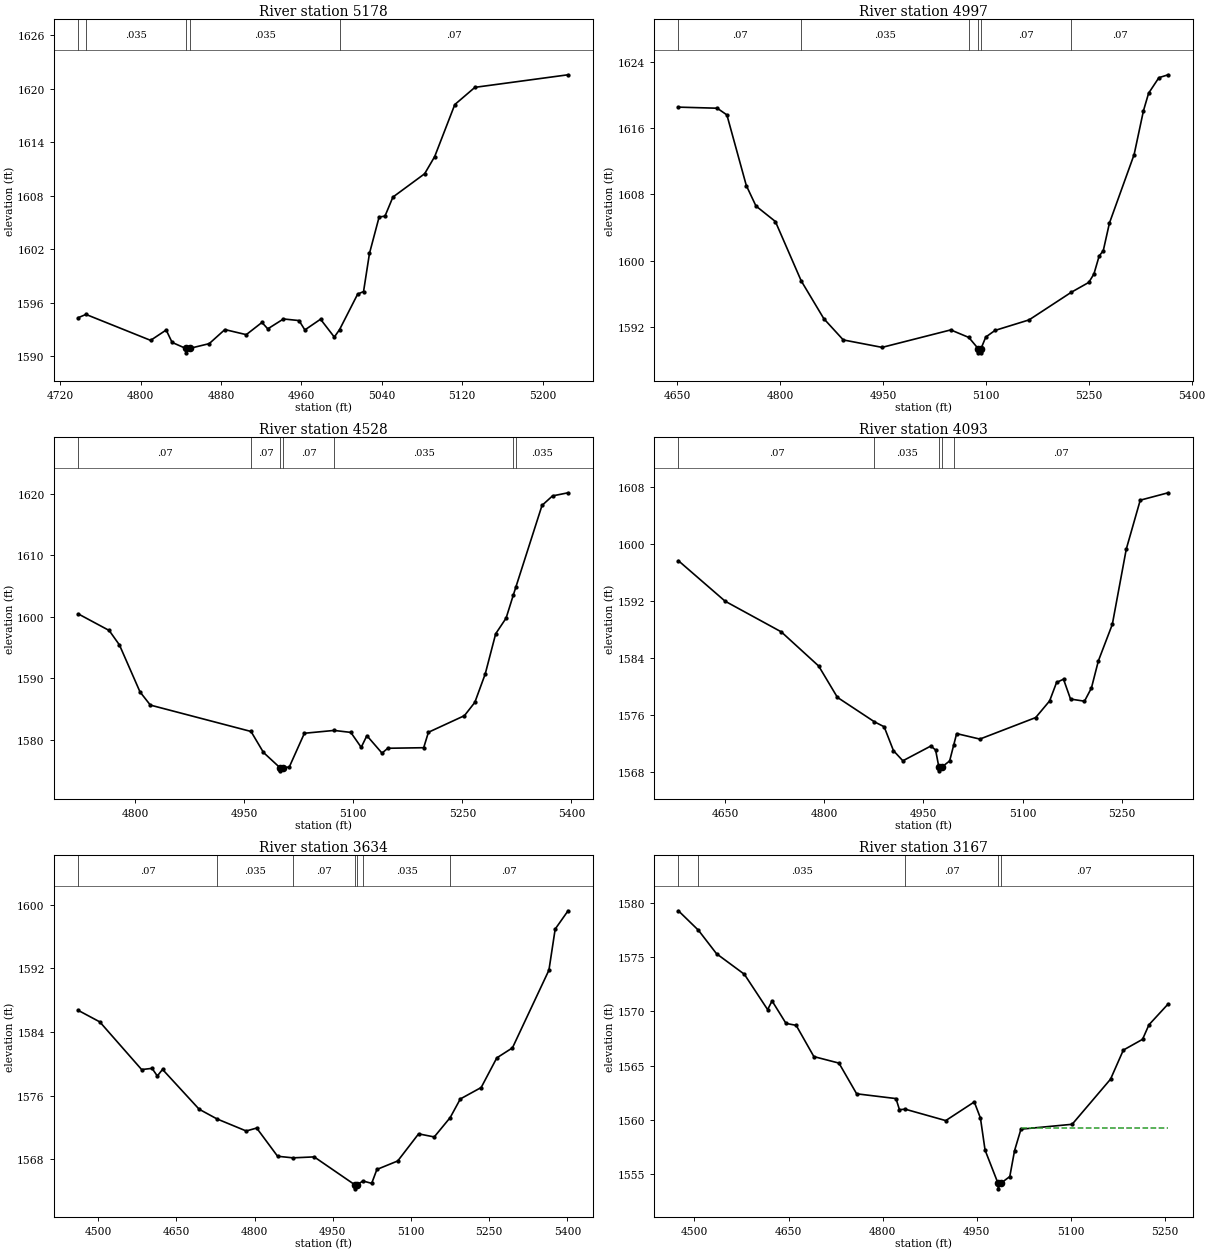
Type RM Length L Ch R = 1 ,5178    ,181,181,181
BEGIN DESCRIPTION:
Stream0083 12.0
END DESCRIPTION:
XS GIS Cut Line= 3
       1996233.4     13919325.94      1995955.59     13919159.26
      1995792.41     13919152.31
#Sta/Elev= 30
  4738.1 1594.31  4745.7 1594.67    4810 1591.76  4825.5 1592.92  4831.4 1591.53
  4844.9 1590.86  4845.2 1590.36  4848.9 1590.86  4868.3 1591.39  4883.9 1592.97
  4905.2  1592.4  4920.8 1593.77  4926.6 1593.05  4942.2 1594.16  4957.7 1593.98
  4963.5 1592.93  4979.1 1594.13  4992.8 1592.13    4998 1592.96    5016 1596.94
  5021.9 1597.24  5027.8 1601.52  5037.4  1605.6  5043.2 1605.69  5051.1 1607.83
  5082.7 1610.45  5092.7 1612.38  5112.7 1618.21  5132.7 1620.14  5225.4 1621.55
#Mann= 5 ,-1 , 0
  4738.1     .07       0  4745.7    .035       0  4844.9     .05       0
  4848.9    .035       0    4998     .07       0
Bank Sta=4844.9,4848.9
XS Rating Curve= 0 ,0
Exp/Cntr=0.3,0.1

Type RM Length L Ch R = 1 ,4997    ,469,469,469
BEGIN DESCRIPTION:
Stream0083 11.0
END DESCRIPTION:
XS GIS Cut Line= 3
        1996375.       13919325.        1996125.       13919075.
      1995825.01     13918875.01
#Sta/Elev= 30
  4651.5 1618.55  4708.1 1618.42  4722.2 1617.61  4750.5 1609.08  4764.6  1606.6
  4792.9 1604.73  4830.6 1597.55  4863.6 1592.98  4891.9 1590.42  4948.5 1589.52
  5048.6 1591.63    5075 1590.72  5088.7 1589.36  5088.9 1588.86  5092.4 1588.86
  5092.7 1589.36  5099.7 1590.77  5113.2 1591.57  5162.8 1592.84  5224.4 1596.18
  5249.9 1597.37  5257.4 1598.39    5265 1600.56    5271  1601.2    5280 1604.54
    5316 1612.82  5329.6 1618.11  5337.1 1620.23  5352.1 1622.11  5365.6 1622.46
#Mann= 6 ,-1 , 0
  4651.5     .07       0  4830.6    .035       0    5075     .07       0
  5088.7     .05       0  5092.7     .07       0  5224.4     .07       0
Bank Sta=5088.7,5092.7
XS Rating Curve= 0 ,0
Exp/Cntr=0.3,0.1

Type RM Length L Ch R = 1 ,4528    ,435,435,435
BEGIN DESCRIPTION:
Stream0083 10.0
END DESCRIPTION:
XS GIS Cut Line= 3
      1996624.99     13918974.99        1996425.       13918775.
      1996125.03     13918525.02
#Sta/Elev= 30
    4722 1600.45  4764.4 1597.76  4778.5 1595.41  4806.8 1587.77    4821 1585.63
  4959.4 1581.34  4976.5 1577.93  4999.3 1575.44  4999.5 1574.94  5003.3 1575.44
    5012 1575.56  5032.8 1581.05  5073.6 1581.51  5096.6 1581.19  5110.9 1578.76
  5118.7 1580.66  5139.5 1577.82  5147.4 1578.61  5196.8  1578.7  5203.3 1581.21
  5252.8 1583.91  5267.1 1586.07  5281.4 1590.69  5295.8 1597.23  5310.1 1599.77
  5320.1 1603.55  5323.7 1604.88  5359.5  1618.1  5373.9 1619.64  5395.3 1620.15
#Mann= 7 ,-1 , 0
    4722     .07       0  4959.4     .07       0  4999.3     .05       0
  5003.3     .07       0  5073.6    .035       0  5320.1     .07       0
  5323.7    .035       0
Bank Sta=4999.3,5003.3
XS Rating Curve= 0 ,0
Exp/Cntr=0.3,0.1

Type RM Length L Ch R = 1 ,4093    ,459,459,459
BEGIN DESCRIPTION:
Stream0083 9.0
END DESCRIPTION:
XS GIS Cut Line= 3
      1996924.97     13918774.97        1996625.       13918475.
      1996324.95     13918374.98
#Sta/Elev= 30
  4579.7 1597.63  4650.4 1591.94  4735.2 1587.64  4791.8 1582.84  4820.1 1578.44
  4876.2    1575  4890.8 1574.31  4904.9 1570.95  4919.1 1569.53  4961.5 1571.61
  4968.6 1571.04  4973.6 1568.62  4973.9 1568.12  4977.6 1568.62  4989.8 1569.51
  4995.8 1571.68  5000.4 1573.35  5035.5 1572.58  5119.9  1575.6    5141 1577.94
  5151.5 1580.53    5162 1580.99  5172.6  1578.2  5193.7  1577.9  5204.2 1579.75
  5214.7 1583.56  5235.8 1588.69  5256.9 1599.26    5278 1606.13  5320.2 1607.17
#Mann= 5 ,-1 , 0
  4579.7     .07       0  4876.2    .035       0  4973.6     .05       0
  4977.6    .035       0  4995.8     .07       0
Bank Sta=4973.6,4977.6
XS Rating Curve= 0 ,0
Exp/Cntr=0.3,0.1

Type RM Length L Ch R = 1 ,3634    ,467,467,467
BEGIN DESCRIPTION:
Stream0083 8.0
END DESCRIPTION:
XS GIS Cut Line= 3
      1997266.01     13918167.33        1996725.       13918125.
       1996328.3     13918119.62
#Sta/Elev= 30
  4461.8 1586.72  4502.9 1585.28  4583.2 1579.28  4603.2 1579.43  4613.3 1578.47
  4623.3  1579.3  4693.5 1574.29  4727.7 1573.07  4783.8 1571.55  4803.9 1571.92
    4844 1568.37  4873.4 1568.17  4914.2 1568.29  4992.4 1564.77  4992.7 1564.27
  4996.4 1564.77  5007.6 1565.26  5024.5 1564.96  5034.5 1566.71  5074.5 1567.78
  5114.5 1571.19  5144.5  1570.8  5175.1 1573.24  5194.5 1575.58  5234.5 1577.02
  5264.5 1580.75  5294.5 1582.01  5364.5 1591.79  5376.5 1596.96  5401.2 1599.26
#Mann= 7 ,-1 , 0
  4461.8     .07       0  4727.7    .035       0  4873.4     .07       0
  4992.4     .05       0  4996.4     .07       0  5007.6    .035       0
  5175.1     .07       0
Bank Sta=4992.4,4996.4
XS Rating Curve= 0 ,0
Exp/Cntr=0.3,0.1

Type RM Length L Ch R = 1 ,3167    ,153,153,153
BEGIN DESCRIPTION:
Stream0083 7.0
END DESCRIPTION:
XS GIS Cut Line= 3
      1997249.92     13917900.23        1996775.       13917675.
      1996524.98       13917725.
#Sta/Elev= 30
  4474.4 1579.27  4506.4 1577.47  4535.2 1575.31  4579.5 1573.42  4616.6 1570.16
  4623.7 1570.96  4645.9 1568.89  4662.1 1568.71  4690.3 1565.83  4730.3 1565.23
  4758.5  1562.4  4821.2 1561.96  4826.7 1560.94    4836 1560.98  4900.5 1559.93
    4946 1561.65  4955.8 1560.17  4963.2 1557.21  4983.9 1554.14  4984.1 1553.64
  4987.9 1554.14  5002.6 1554.77  5010.2 1557.16  5020.4 1559.14    5102 1559.59
  5163.2 1563.75  5183.6 1566.43  5214.2 1567.42  5224.4 1568.76    5255 1570.68
#Mann= 5 ,-1 , 0
  4474.4     .07       0  4506.4    .035       0    4836     .07       0
  4983.9     .05       0  4987.9     .07       0
#XS Ineff= 2 , 0
                         5022.38         1559.28
Permanent Ineff=
       F       F
Bank Sta=4983.9,4987.9
XS Rating Curve= 0 ,0
Exp/Cntr=0.3,0.1

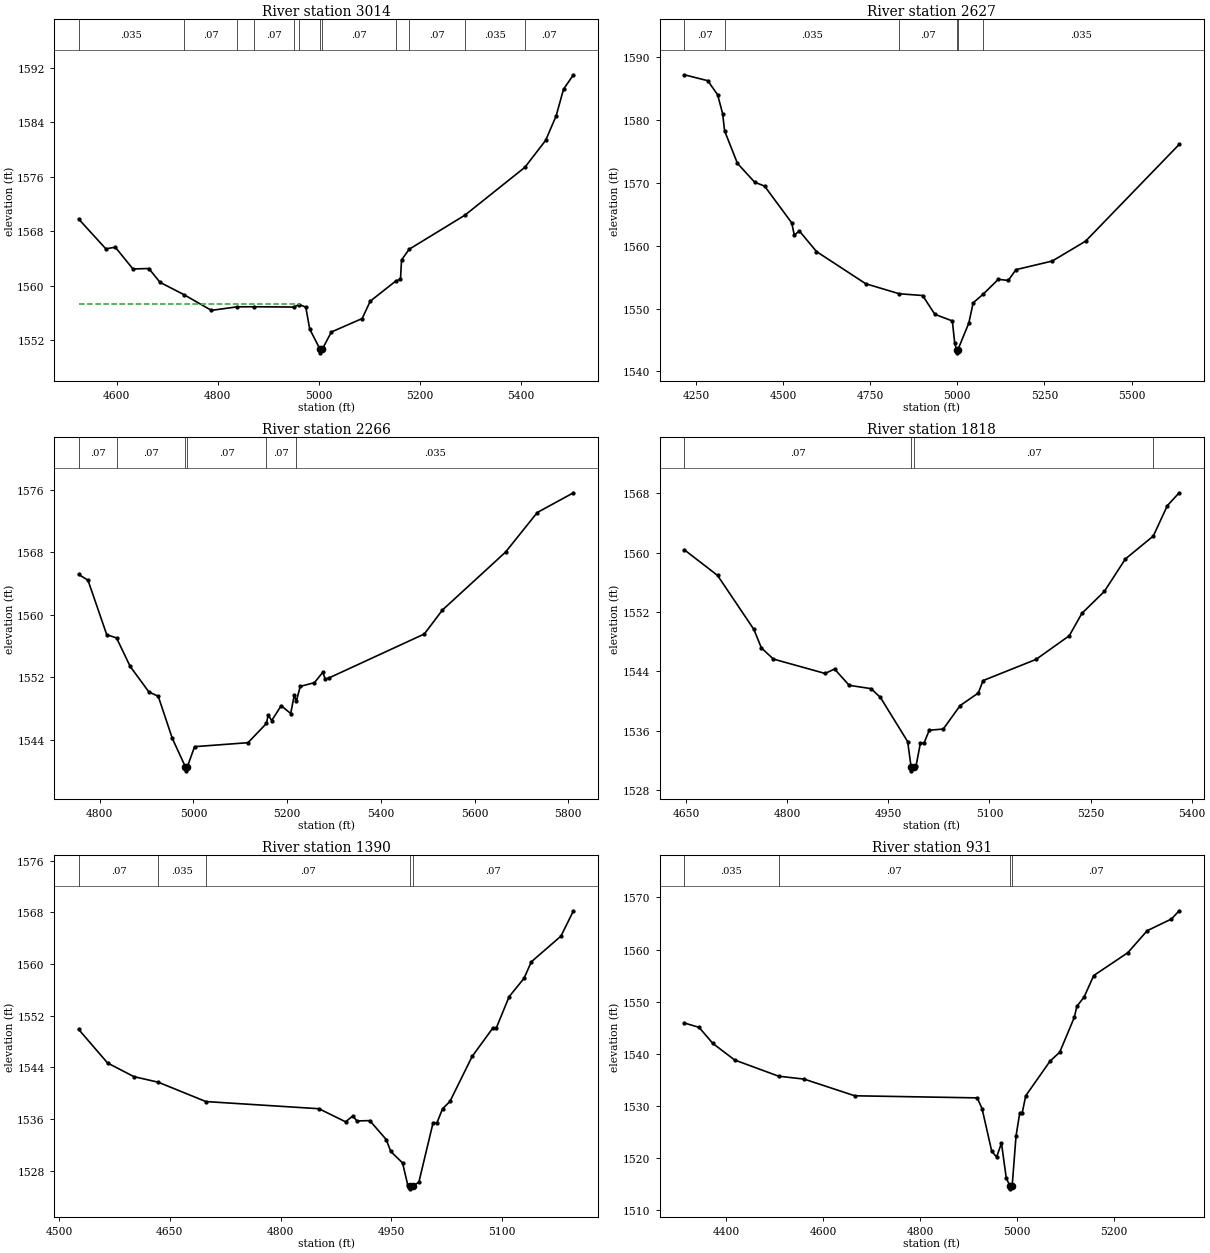
Type RM Length L Ch R = 1 ,3014    ,387,387,387
BEGIN DESCRIPTION:
Mapping XS e09e2fbb
END DESCRIPTION:
XS GIS Cut Line= 4
      1997213.92     13917668.73      1996828.53     13917512.49
      1996606.31     13917550.69       1996333.4     13917751.05
#Sta/Elev= 30
  4524.3 1569.81  4578.3 1565.43    4597 1565.67  4631.9 1562.48  4663.4 1562.54
  4685.5 1560.52  4733.4 1558.69  4787.3  1556.4  4838.1 1556.92  4871.2 1556.93
  4950.4 1556.89  4961.2 1557.26  4974.2 1556.87  4981.9 1553.67  5002.6 1550.67
  5002.9 1550.17  5006.6 1550.67  5024.9 1553.23  5085.8  1555.2  5101.8 1557.75
  5152.3  1560.7  5161.7 1560.98  5163.8  1563.8  5178.9 1565.37  5289.1 1570.36
    5408 1577.39  5449.1 1581.34  5469.9 1584.93  5484.6 1588.86  5504.2 1590.97
#Mann= 12 ,-1 , 0
  4524.3    .035       0  4733.4     .07       0  4838.1    .035       0
  4871.2     .07       0  4950.4    .035       0  4961.2     .07       0
  5002.6     .05       0  5006.6     .07       0  5152.3    .035       0
  5178.9     .07       0  5289.1    .035       0    5408     .07       0
#XS Ineff= 2 , 0
         4961.04 1557.39
Permanent Ineff=
       F       F
Bank Sta=5002.6,5006.6
XS Rating Curve= 0 ,0
Exp/Cntr=0.3,0.1

Type RM Length L Ch R = 1 ,2627    ,361,361,361
BEGIN DESCRIPTION:
Stream0083 6.0
END DESCRIPTION:
XS GIS Cut Line= 3
      1997413.69     13917741.51      1996821.41     13917220.32
      1996215.36     13917044.09
#Sta/Elev= 30
  4216.6 1587.15  4283.8 1586.21  4312.2 1583.98  4326.5 1580.99  4332.3 1578.22
  4369.1 1573.07  4418.5 1570.08    4447 1569.46  4524.8 1563.62  4532.3 1561.65
  4546.6 1562.34  4595.9 1559.06  4737.3 1553.94  4833.3 1552.35  4900.5 1552.07
  4935.6 1549.08  4985.8 1548.03  4992.5 1544.53  4997.8 1543.46  4998.1 1542.96
  5001.8 1543.46  5033.1  1547.7  5045.6 1550.92  5073.9 1552.26  5117.8 1554.65
  5146.2 1554.46  5168.4 1556.18  5272.6 1557.55  5368.2 1560.71  5636.7 1576.08
#Mann= 6 ,-1 , 0
  4216.6     .07       0  4332.3    .035       0  4833.3     .07       0
  4997.8     .05       0  5001.8     .07       0  5073.9    .035       0
Bank Sta=4997.8,5001.8
XS Rating Curve= 0 ,0
Exp/Cntr=0.3,0.1

Type RM Length L Ch R = 1 ,2266    ,448,448,448
BEGIN DESCRIPTION:
Stream0083 5.0
END DESCRIPTION:
XS GIS Cut Line= 4
      1997274.97       13917025.        1997025.       13917025.
        1996725.       13917075.       1996233.1     13916974.84
#Sta/Elev= 30
  4754.9 1565.18  4774.9 1564.44  4814.9 1557.46  4835.9 1557.03  4864.9 1553.39
  4904.9 1550.11  4924.9 1549.55  4954.9 1544.15  4982.9 1540.49  4983.1 1539.99
  4986.9 1540.49  5002.4 1543.09  5116.4  1543.6  5155.8 1546.07  5159.5 1547.14
  5167.1 1546.44  5187.3 1548.35  5207.6 1547.34  5215.2 1549.73  5219.5 1548.89
  5227.9 1550.82  5258.3  1551.3  5276.1 1552.64  5281.1 1551.76  5288.7 1551.89
  5492.7 1557.54  5531.5 1560.62  5666.2 1568.05  5733.8 1573.12    5811 1575.65
#Mann= 6 ,-1 , 0
  4754.9     .07       0  4835.9     .07       0  4982.9     .05       0
  4986.9     .07       0  5155.8     .07       0  5219.5    .035       0
Bank Sta=4982.9,4986.9
XS Rating Curve= 0 ,0
Exp/Cntr=0.3,0.1

Type RM Length L Ch R = 1 ,1818    ,428,428,428
BEGIN DESCRIPTION:
Stream0083 4.0
END DESCRIPTION:
XS GIS Cut Line= 3
      1997350.44     13916811.88        1997025.       13916675.
      1996658.15     13916571.62
#Sta/Elev= 30
  4647.2  1560.4  4696.5 1556.94  4750.3 1549.67  4761.6 1547.15  4779.4 1545.65
  4856.1 1543.71  4870.1 1544.31  4891.8 1542.11  4924.3 1541.66  4938.2 1540.47
  4978.6 1534.51  4983.7 1531.07  4983.9 1530.57  4987.7 1531.07  4991.1 1531.27
  4997.5 1534.32  5002.9 1534.32  5010.6 1536.05  5031.4 1536.21  5056.5 1539.38
  5083.4 1541.07  5090.5 1542.75  5168.9  1545.6  5218.4  1548.8    5237 1551.81
  5270.4 1554.78  5301.6 1559.16    5343 1562.25  5363.9 1566.36  5381.4 1568.09
#Mann= 4 ,-1 , 0
  4647.2     .07       0  4983.7     .05       0  4987.7     .07       0
    5343    .035       0
Bank Sta=4983.7,4987.7
XS Rating Curve= 0 ,0
Exp/Cntr=0.3,0.1

Type RM Length L Ch R = 1 ,1390    ,459,459,459
BEGIN DESCRIPTION:
Stream0083 3.0
END DESCRIPTION:
XS GIS Cut Line= 3
       1997462.9     13916477.75        1997025.       13916275.
      1996838.12     13916263.42
#Sta/Elev= 30
  4526.6 1549.88  4565.8 1544.67  4601.4 1542.56  4634.5 1541.69  4698.9  1538.7
  4851.9 1537.59  4887.9 1535.57  4897.8 1536.46  4903.3  1535.7  4920.7 1535.75
    4943 1532.82  4949.1 1530.98  4965.1  1529.2    4972 1525.84  4975.5 1525.69
  4975.8 1525.19  4979.5 1525.69  4987.1  1526.2  5006.4 1535.42  5011.7 1535.42
  5019.2 1537.58  5029.2 1538.71  5059.3 1545.69  5087.1 1550.05  5092.2 1550.15
  5109.3 1554.93  5129.4 1557.76  5139.4 1560.33  5179.5 1564.31  5196.4 1568.23
#Mann= 5 ,-1 , 0
  4526.6     .07       0  4634.5    .035       0  4698.9     .07       0
  4975.5     .05       0  4979.5     .07       0
Bank Sta=4975.5,4979.5
XS Rating Curve= 0 ,0
Exp/Cntr=0.3,0.1

Type RM Length L Ch R = 1 ,931     ,410,410,410
BEGIN DESCRIPTION:
Stream0083 2.0
END DESCRIPTION:
XS GIS Cut Line= 4
      1997513.68     13916377.43      1997257.67     13915878.63
        1997125.       13915875.      1996799.19     13915860.92
#Sta/Elev= 30
  4314.4 1545.93  4344.8 1545.09  4373.3    1542  4418.3 1538.83  4508.8 1535.73
  4561.1 1535.18  4665.6 1531.98  4917.8 1531.58  4927.8 1529.53  4947.8 1521.34
  4957.8 1520.24  4967.8 1522.92  4977.8 1516.15  4985.8 1514.65    4986 1514.15
  4989.8 1514.65  4997.8 1524.26  5005.3 1528.59  5010.3 1528.59  5017.8 1531.98
  5067.8 1538.61  5087.9 1540.34  5117.9 1547.01  5123.2 1549.13  5137.9 1550.88
  5157.9 1555.02    5228 1559.39    5268 1563.61  5318.1 1565.86  5333.9 1567.43
#Mann= 4 ,-1 , 0
  4314.4    .035       0  4508.8     .07       0  4985.8     .05       0
  4989.8     .07       0
Bank Sta=4985.8,4989.8
XS Rating Curve= 0 ,0
Exp/Cntr=0.3,0.1

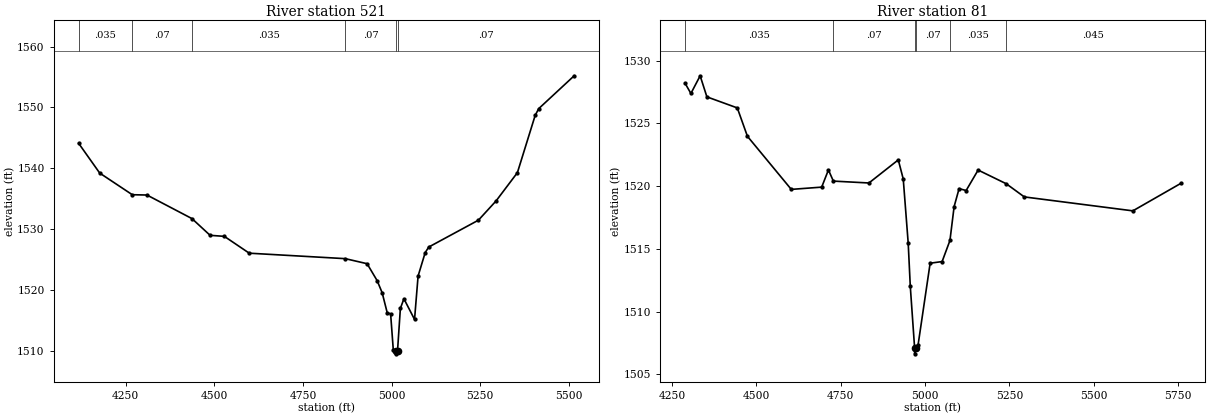
Type RM Length L Ch R = 1 ,521     ,440,440,440
BEGIN DESCRIPTION:
Stream0083 1.0
END DESCRIPTION:
XS GIS Cut Line= 4
      1997538.16     13916334.23      1997473.68     13915661.18
        1997325.       13915525.      1996804.96     13915545.35
#Sta/Elev= 30
  4117.1  1544.1  4176.6  1539.2  4268.5 1535.64  4309.9 1535.59  4436.9 1531.71
    4488 1528.96  4528.2 1528.79  4598.5 1526.02  4869.6 1525.12    4931 1524.29
  4959.4  1521.5  4973.6  1519.5  4987.8 1516.22  4997.4 1516.04  5004.9 1510.13
  5012.9 1509.96  5013.1 1509.46  5016.9 1509.96  5024.9 1516.93  5034.9 1518.52
  5064.9 1515.12  5074.9 1522.26  5094.9 1526.11  5104.9 1527.03  5245.1 1531.45
  5295.1 1534.63  5355.1 1539.27  5405.2 1548.68  5415.2  1549.8  5515.3 1555.21
#Mann= 6 ,-1 , 0
  4117.1    .035       0  4268.5     .07       0  4436.9    .035       0
  4869.6     .07       0  5012.9     .05       0  5016.9     .07       0
Bank Sta=5012.9,5016.9
XS Rating Curve= 0 ,0
Exp/Cntr=0.3,0.1

Type RM Length L Ch R = 1 ,81      ,0,0,0
BEGIN DESCRIPTION:
Stream0083 0.0
END DESCRIPTION:
XS GIS Cut Line= 4
      1997680.44      13915889.6      1997662.47     13915282.67
      1997436.79     13914971.26      1996963.69     13914911.83
#Sta/Elev= 30
  4288.6 1528.19  4305.8 1527.38  4333.2 1528.79  4353.2 1527.11  4443.3 1526.23
  4473.3 1523.97  4603.3 1519.74  4693.4 1519.92  4713.4 1521.29    4728  1520.4
  4833.4 1520.25  4920.4 1522.09  4935.1 1520.57  4949.8 1515.46    4956 1512.01
  4968.7 1507.14  4968.9 1506.64  4972.7 1507.14  4979.2 1507.37  5014.8 1513.86
  5050.3 1513.99  5073.5 1515.67  5085.9 1518.37  5100.6  1519.8  5121.5 1519.65
    5157 1521.28  5240.3 1520.19  5293.9 1519.14  5615.6 1518.03  5757.2 1520.21
#Mann= 6 ,-1 , 0
  4288.6    .035       0    4728     .07       0  4968.7     .05       0
  4972.7     .07       0  5073.5    .035       0  5240.3    .045       0
Bank Sta=4968.7,4972.7
XS Rating Curve= 0 ,0
Exp/Cntr=0.3,0.1

Chan Stop Cuts=-1
Use User Specified Reach Order=0
Composite Channel Slope=5