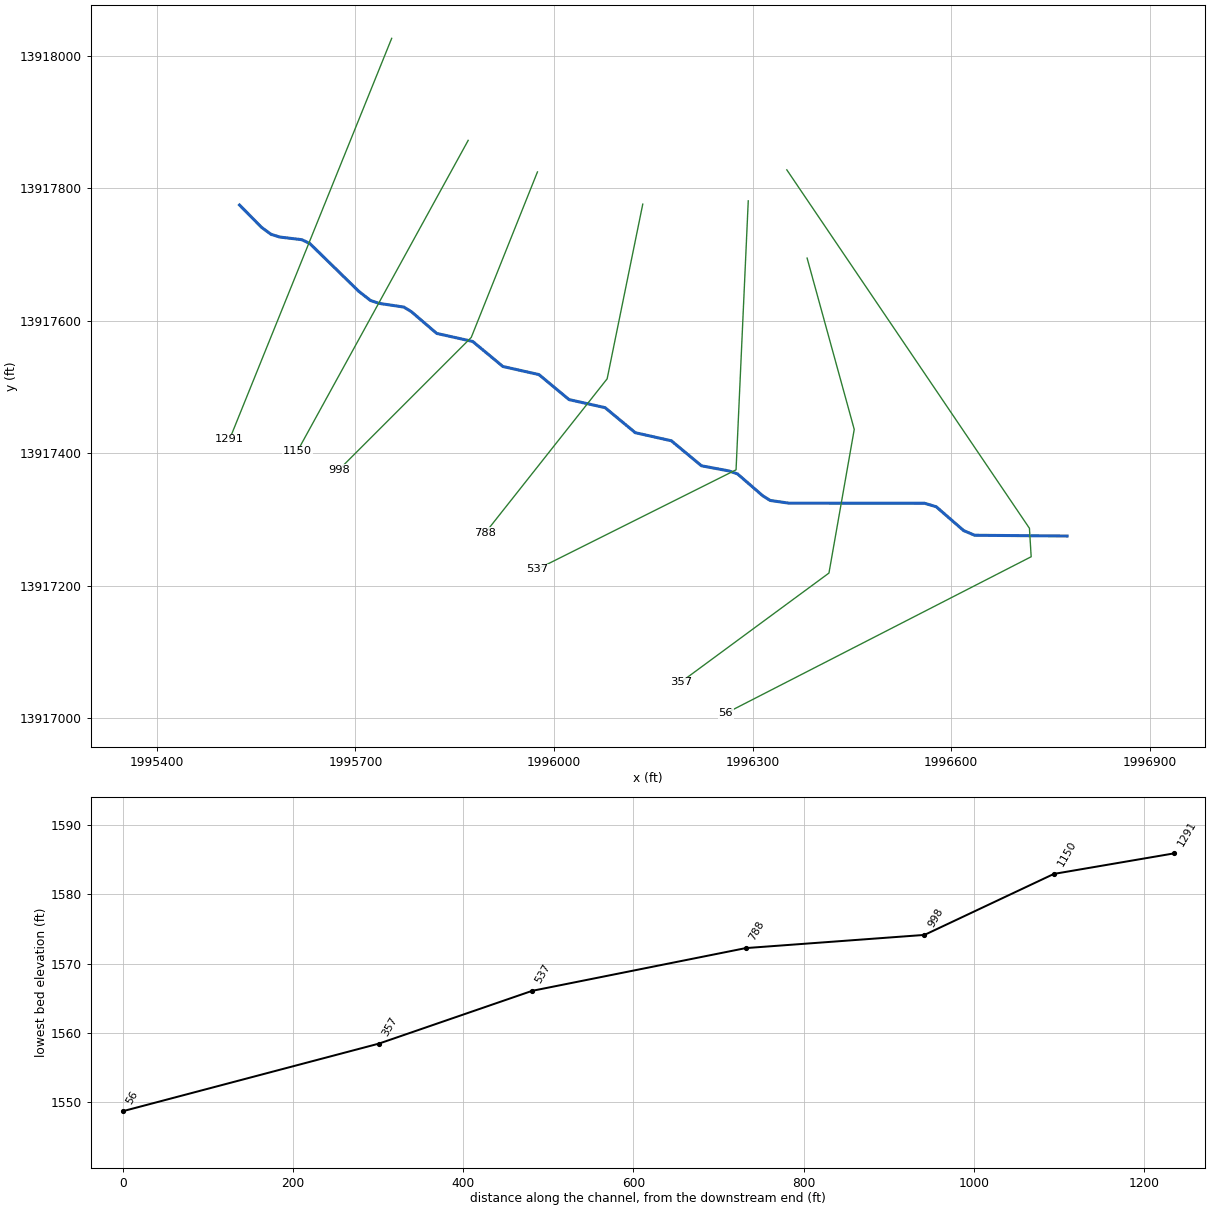
--- Stream0084.prj (project) ---

Proj Title=Stream0084 Base Level Engineering
Current Plan=p01
Default Exp/Contr=0.3,0.1
English Units
Geom File=g01
Flow File=f01
Plan File=p01
BEGIN DESCRIPTION:
Stream0084
END DESCRIPTION:

--- Stream0084.p01 (plan) ---

Plan Title=Multiple Run
Short Identifier=Multiple
Geom File=g01
Flow File=f01
Subcritical Flow
K Sum by GR= 0
Std Step Tol= 0.01
Critical Tol= 0.01
Num of Std Step Trials= 20
Max Error Tol= 0.3
Flow Tol Ratio= 0.001
Split Flow NTrial= 30
Split Flow Tol= 0.02
Split Flow Ratio= 0.02
Log Output Level= 0
Friction Slope Method= 1
Unsteady Friction Slope Method= 2
Unsteady Bridges Friction Slope Method= 1
Parabolic Critical Depth
Global Vel Dist=  1 , 1 , 1
Global Log Level= 0
CheckData=True
Encroach Param= -1, 0, 0, 0
BEGIN DESCRIPTION:
Multiple Run
END DESCRIPTION:

--- Stream0084.f01 (steady flow) ---

Flow Title=Multiple
Number of Profiles=7
Profile Names=10-year,25-year,50-year,1pct_min,100-year,1pct_plu,500-year
River Rch & RM= Stream0084,Reach-1,1291
     328     523     699     456     909    1814    1520
Boundary for River Rch & Prof#=Stream0084,Reach-1,1
Up Type=0
Dn Type=3
Dn Slope=0.005
Boundary for River Rch & Prof#=Stream0084,Reach-1,2
Up Type=0
Dn Type=3
Dn Slope=0.005
Boundary for River Rch & Prof#=Stream0084,Reach-1,3
Up Type=0
Dn Type=3
Dn Slope=0.005
Boundary for River Rch & Prof#=Stream0084,Reach-1,4
Up Type=0
Dn Type=3
Dn Slope=0.005
Boundary for River Rch & Prof#=Stream0084,Reach-1,5
Up Type=0
Dn Type=3
Dn Slope=0.005
Boundary for River Rch & Prof#=Stream0084,Reach-1,6
Up Type=0
Dn Type=3
Dn Slope=0.005
Boundary for River Rch & Prof#=Stream0084,Reach-1,7
Up Type=0
Dn Type=3
Dn Slope=0.005

--- Stream0084.g01 (geometry) ---

Geom Title=Existing Conditions

River Reach=Stream0084,Reach-1
Reach XY= 30
      1995525.00     13917775.00      1995558.08     13917741.42
      1995572.65     13917730.70      1995585.68     13917726.65
      1995619.03     13917722.65      1995631.08     13917716.93
      1995704.93     13917644.82      1995722.71     13917630.85
      1995735.63     13917626.51      1995773.26     13917620.81
      1995784.54     13917613.90      1995822.80     13917581.08
      1995877.20     13917568.92      1995922.80     13917531.08
      1995977.20     13917518.92      1996022.80     13917481.08
      1996077.20     13917468.92      1996122.80     13917431.08
      1996177.20     13917418.92      1996222.80     13917381.08
      1996264.31     13917373.33      1996277.18     13917368.88
      1996315.33     13917335.80      1996326.55     13917328.75
      1996354.85     13917324.64      1996559.78     13917324.48
      1996577.34     13917319.26      1996618.94     13917283.13
      1996635.48     13917276.17      1996775.00     13917275.00

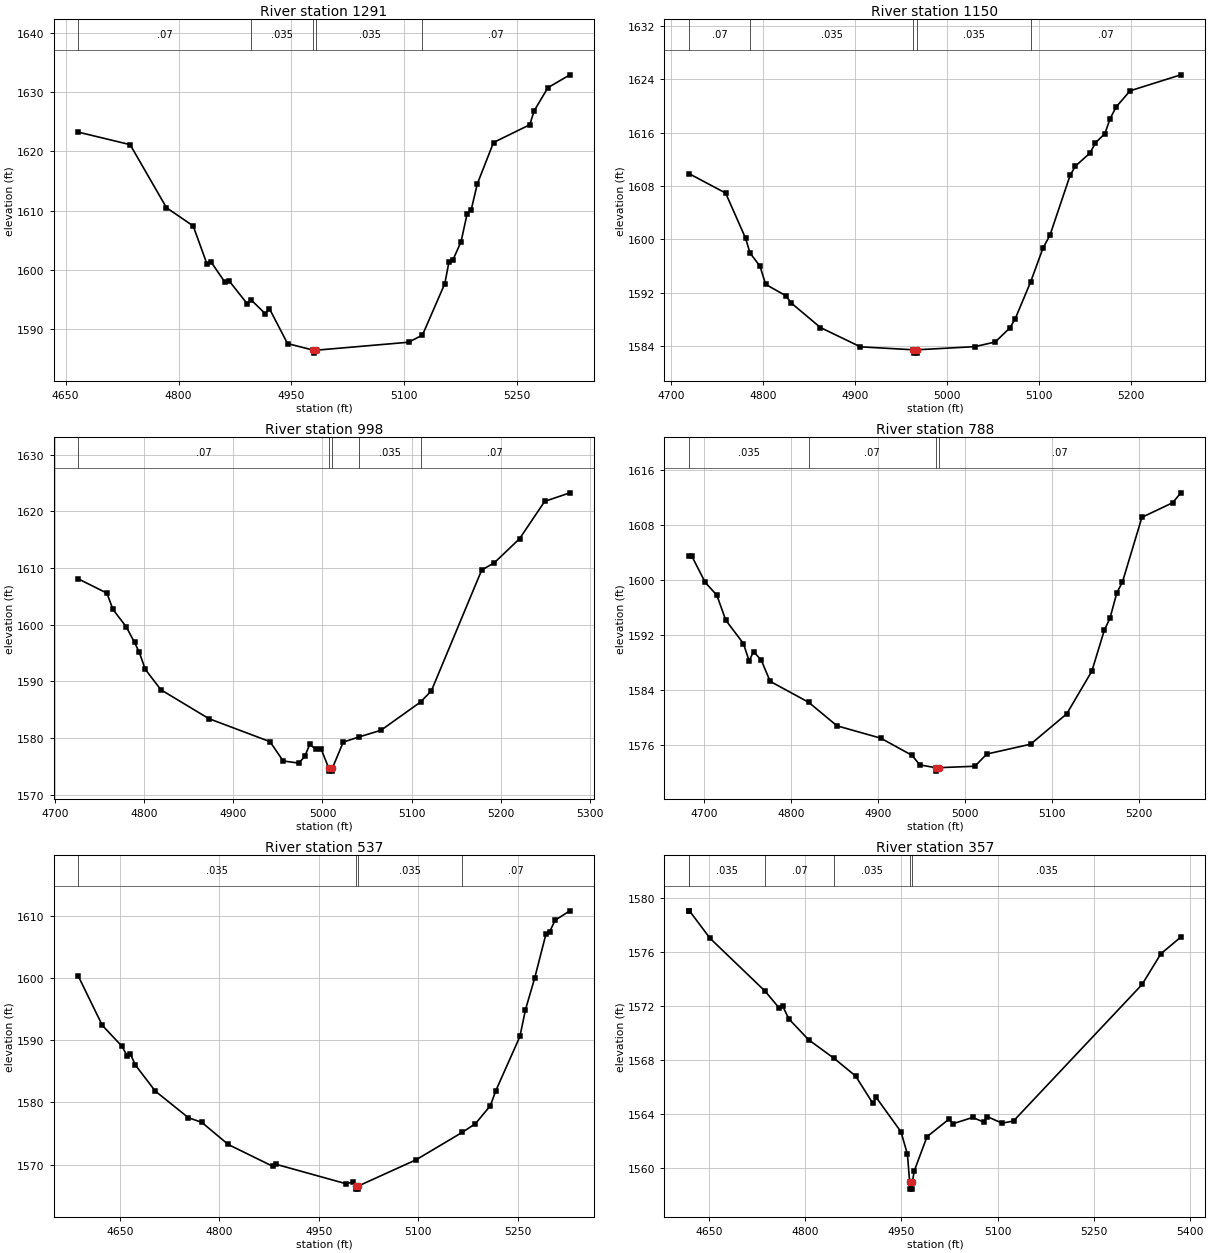
Type RM Length L Ch R = 1,1291,141,141,141
BEGIN DESCRIPTION:
Stream0084 3.0
END DESCRIPTION:
XS GIS Cut Line= 2
      1995754.81     13918026.80      1995509.87     13917420.94
#Sta/Elev= 30
  4666.6 1623.27  4735.7 1621.15  4784.0 1610.50  4819.5 1607.42  4837.6 1601.07
  4843.0 1601.39  4861.7 1597.91  4867.1 1598.17  4891.3 1594.27  4896.1 1594.98
  4915.4 1592.58  4920.8 1593.45  4944.9 1587.55  4979.3 1586.44  4979.6 1585.94
  4983.3 1586.44  5105.8 1587.78  5124.2 1588.99  5153.9 1597.69  5159.5 1601.41
  5164.9 1601.75  5175.5 1604.77  5183.6 1609.51  5189.0 1610.17  5197.1 1614.53
  5218.6 1621.51  5266.8 1624.51  5272.6 1626.86  5290.9 1630.77  5320.1 1632.94
#Mann=5,-1,0
  4666.6    0.07       0  4896.1   0.035       0  4979.3   0.035       0
  4983.3   0.035       0  5124.2    0.07       0
Bank Sta=4979.3,4983.3
Exp/Cntr=0.3,0.1

Type RM Length L Ch R = 1,1150,152,152,152
BEGIN DESCRIPTION:
Mapping XS e33dd2cc
END DESCRIPTION:
XS GIS Cut Line= 2
      1995870.39     13917872.71      1995612.47     13917403.30
#Sta/Elev= 30
  4719.2 1609.84  4759.0 1606.94  4780.8 1600.16  4785.5 1597.98  4796.5 1595.97
  4802.6 1593.27  4824.4 1591.58  4830.7 1590.45  4862.3 1586.80  4905.9 1583.91
  4963.5 1583.47  4963.8 1582.97  4967.3 1582.97  4967.5 1583.47  5030.4 1583.94
  5052.7 1584.64  5068.8 1586.78  5074.5 1588.14  5091.3 1593.66  5104.5 1598.64
  5112.4 1600.68  5134.2 1609.58  5139.9 1610.96  5156.0 1612.95  5161.7 1614.44
  5172.1 1615.84  5177.8 1618.09  5184.4 1619.84  5199.6 1622.25  5254.8 1624.64
#Mann=5,-1,0
  4719.2    0.07       0  4785.5   0.035       0  4963.5   0.035       0
  4967.5   0.035       0  5091.3    0.07       0
Bank Sta=4963.5,4967.5
Exp/Cntr=0.3,0.1

Type RM Length L Ch R = 1,998,210,210,210
BEGIN DESCRIPTION:
Stream0084 2.0
END DESCRIPTION:
XS GIS Cut Line= 3
      1995975.01     13917825.03      1995875.00     13917575.00
      1995675.02     13917375.02
#Sta/Elev= 30
  4725.7 1608.08  4758.0 1605.55  4764.8 1602.67  4779.6 1599.63  4789.0 1596.86
  4794.4 1595.09  4801.1 1592.10  4818.6 1588.50  4872.5 1583.40  4941.1 1579.34
  4955.9 1575.93  4973.4 1575.56  4980.2 1576.73  4985.6 1578.84  4992.3 1578.06
  4998.5 1578.06  5007.1 1574.64  5007.4 1574.14  5010.9 1574.14  5011.1 1574.64
  5023.3 1579.26  5041.0 1580.17  5065.7 1581.35  5110.1 1586.33  5122.3 1588.31
  5178.8 1609.63  5193.0 1610.91  5221.3 1615.15  5249.5 1621.74  5277.8 1623.25
#Mann=5,-1,0
  4725.7    0.07       0  5007.1    0.05       0  5011.1    0.07       0
  5041.0   0.035       0  5110.1    0.07       0
Bank Sta=5007.1,5011.1
Exp/Cntr=0.3,0.1

Type RM Length L Ch R = 1,788,251,251,251
BEGIN DESCRIPTION:
Mapping XS 3e2a7ae4
END DESCRIPTION:
XS GIS Cut Line= 3
      1996134.09     13917776.38      1996080.27     13917512.49
      1995896.27     13917279.89
#Sta/Elev= 30
  4682.8 1603.42  4686.1 1603.42  4701.4 1599.64  4714.8 1597.77  4725.0 1594.16
  4745.4 1590.75  4751.9 1588.24  4757.0 1589.59  4765.9 1588.34  4776.1 1585.27
  4820.4 1582.23  4853.0 1578.81  4903.5 1577.01  4939.4 1574.52  4948.3 1573.14
  4966.4 1572.73  4966.6 1572.23  4970.4 1572.73  5011.7 1572.94  5025.4 1574.71
  5075.8 1576.14  5117.4 1580.55  5146.3 1586.75  5160.7 1592.72  5167.1 1594.41
  5175.1 1598.15  5181.5 1599.69  5203.9 1609.09  5239.3 1611.21  5248.7 1612.65
#Mann=4,-1,0
  4682.8   0.035       0  4820.4    0.07       0  4966.4    0.05       0
  4970.4    0.07       0
Bank Sta=4966.4,4970.4
Exp/Cntr=0.3,0.1

Type RM Length L Ch R = 1,537,180,180,180
BEGIN DESCRIPTION:
Stream0084 1.0
END DESCRIPTION:
XS GIS Cut Line= 3
      1996293.44     13917781.31      1996275.00     13917375.00
      1995975.04     13917225.02
#Sta/Elev= 30
  4586.9 1600.39  4623.3 1592.42  4653.3 1589.01  4660.5 1587.55  4665.5 1587.86
  4673.3 1586.02  4703.3 1581.83  4753.4 1577.53  4773.4 1576.80  4813.4 1573.23
  4880.9 1569.70  4885.9 1570.03  4991.1 1566.91  5002.0 1567.20  5005.6 1566.54
  5005.9 1566.04  5009.4 1566.04  5009.6 1566.54  5097.0 1570.77  5166.7 1575.19
  5186.5 1576.58  5208.9 1579.46  5217.2 1581.89  5253.6 1590.62  5262.0 1594.95
  5275.9 1600.03  5292.7 1607.04  5298.3 1607.45  5306.7 1609.34  5329.0 1610.85
#Mann=4,-1,0
  4586.9   0.035       0  5005.6   0.035       0  5009.6   0.035       0
  5166.7    0.07       0
Bank Sta=5005.6,5009.6
Exp/Cntr=0.3,0.1

Type RM Length L Ch R = 1,357,301,301,301
BEGIN DESCRIPTION:
Mapping XS ff6bc8a2
END DESCRIPTION:
XS GIS Cut Line= 4
      1996382.34     13917694.82      1996453.53     13917436.10
      1996415.34     13917219.09      1996191.39     13917054.17
#Sta/Elev= 30
  4618.8 1579.07  4619.4 1579.07  4651.3 1577.04  4737.4 1573.10  4759.7 1571.83
  4764.9 1571.99  4774.2 1571.05  4805.3 1569.49  4845.0 1568.11  4878.5 1566.80
  4905.5 1564.76  4910.6 1565.21  4949.2 1562.66  4959.3 1560.99  4962.8 1558.90
  4963.0 1558.40  4966.5 1558.40  4966.8 1558.90  4969.9 1559.75  4989.8 1562.29
  5024.1 1563.60  5030.4 1563.26  5060.9 1563.72  5078.3 1563.38  5083.4 1563.79
  5107.0 1563.30  5124.7 1563.46  5325.2 1573.60  5354.5 1575.88  5385.6 1577.12
#Mann=6,-1,0
  4618.8    0.07       0  4619.4   0.035       0  4737.4    0.07       0
  4845.0   0.035       0  4962.8   0.035       0  4966.8   0.035       0
Bank Sta=4962.8,4966.8
Exp/Cntr=0.3,0.1

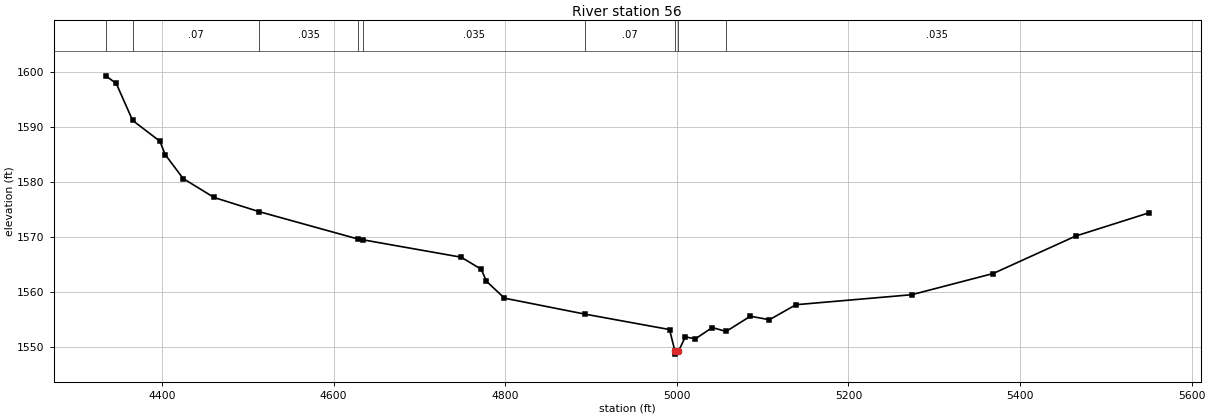
Type RM Length L Ch R = 1,56,0,0,0
BEGIN DESCRIPTION:
Stream0084 0.0
END DESCRIPTION:
XS GIS Cut Line= 4
      1996351.69     13917828.14      1996718.18     13917286.70
      1996720.79     13917243.73      1996259.28     13917007.12
#Sta/Elev= 30
  4334.3 1599.35  4346.6 1597.96  4365.7 1591.22  4397.5 1587.42  4403.6 1585.00
  4424.6 1580.62  4460.5 1577.18  4512.6 1574.61  4628.7 1569.58  4634.6 1569.44
  4748.7 1566.28  4772.0 1564.08  4778.1 1561.89  4799.1 1558.81  4893.0 1555.90
  4991.5 1553.09  4997.8 1549.11  4998.1 1548.61  5001.8 1549.11  5009.9 1551.76
  5021.5 1551.39  5041.3 1553.46  5057.3 1552.74  5085.7 1555.52  5107.9 1554.88
  5138.8 1557.62  5273.7 1559.44  5368.7 1563.31  5464.7 1570.13  5549.8 1574.35
#Mann=9,-1,0
  4334.3   0.035       0  4365.7    0.07       0  4512.6   0.035       0
  4628.7    0.07       0  4634.6   0.035       0  4893.0    0.07       0
  4997.8    0.05       0  5001.8    0.07       0  5057.3   0.035       0
Bank Sta=4997.8,5001.8
Exp/Cntr=0.3,0.1

Chan Stop Cuts=-1