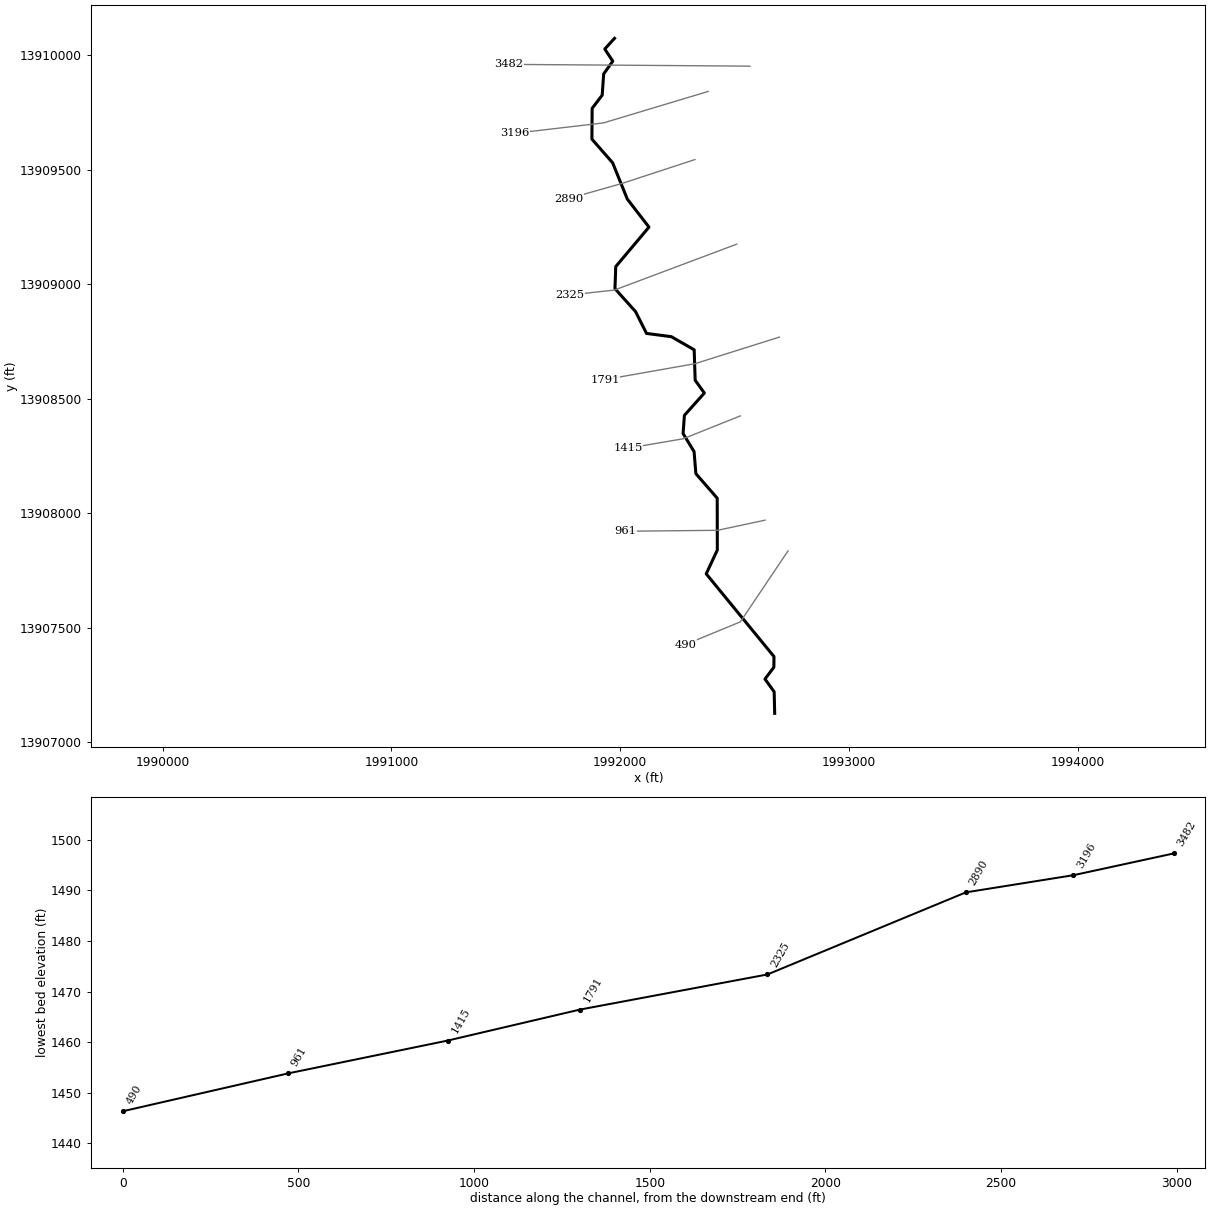
--- Stream0085.prj (project) ---

Proj Title=Stream0085 Base Level Engineering
Current Plan=p01
Default Exp/Contr=0.3,0.1
English Units
Geom File=g01
Flow File=f01
Plan File=p01
BEGIN DESCRIPTION:
Stream0085
END DESCRIPTION:

--- Stream0085.p01 (plan) ---

Plan Title=Multiple Run
Short Identifier=Multiple
Geom File=g01
Flow File=f01
Subcritical Flow
K Sum by GR= 0
Std Step Tol= 0.01
Critical Tol= 0.01
Num of Std Step Trials= 20
Max Error Tol= 0.3
Flow Tol Ratio= 0.001
Split Flow NTrial= 30
Split Flow Tol= 0.02
Split Flow Ratio= 0.02
Log Output Level= 0
Friction Slope Method= 1
Unsteady Friction Slope Method= 2
Unsteady Bridges Friction Slope Method= 1
Parabolic Critical Depth
Global Vel Dist=  1 , 1 , 1
Global Log Level= 0
CheckData=True
Encroach Param= -1, 0, 0, 0
BEGIN DESCRIPTION:
Multiple Run
END DESCRIPTION:

--- Stream0085.f01 (steady flow) ---

Flow Title=Multiple
Number of Profiles=7
Profile Names=10-year,25-year,50-year,1pct_min,100-year,1pct_plu,500-year
River Rch & RM= Stream0085,Reach-1,3482
     530     861    1164     764    1525    3043    2593
Boundary for River Rch & Prof#=Stream0085,Reach-1,1
Up Type=0
Dn Type=3
Dn Slope=0.005
Boundary for River Rch & Prof#=Stream0085,Reach-1,2
Up Type=0
Dn Type=3
Dn Slope=0.005
Boundary for River Rch & Prof#=Stream0085,Reach-1,3
Up Type=0
Dn Type=3
Dn Slope=0.005
Boundary for River Rch & Prof#=Stream0085,Reach-1,4
Up Type=0
Dn Type=3
Dn Slope=0.005
Boundary for River Rch & Prof#=Stream0085,Reach-1,5
Up Type=0
Dn Type=3
Dn Slope=0.005
Boundary for River Rch & Prof#=Stream0085,Reach-1,6
Up Type=0
Dn Type=3
Dn Slope=0.005
Boundary for River Rch & Prof#=Stream0085,Reach-1,7
Up Type=0
Dn Type=3
Dn Slope=0.005

--- Stream0085.g01 (geometry) ---

Geom Title=Existing Conditions

River Reach=Stream0085,Reach-1
Reach XY= 30
      1991975.00     13910075.00      1991932.51     13910028.34
      1991967.37     13909975.11      1991927.66     13909919.52
      1991921.15     13909826.60      1991877.25     13909769.06
      1991876.20     13909634.60      1991966.84     13909531.05
      1992030.85     13909372.71      1992125.59     13909250.00
      1991980.40     13909077.43      1991976.97     13908980.90
      1992066.81     13908881.02      1992114.90     13908785.39
      1992223.44     13908771.18      1992323.15     13908713.87
      1992327.48     13908580.87      1992367.67     13908524.90
      1992280.43     13908427.43      1992274.71     13908347.77
      1992322.64     13908269.02      1992330.54     13908172.58
      1992423.79     13908065.41      1992424.30     13907838.91
      1992375.75     13907734.78      1992671.84     13907373.35
      1992671.43     13907326.65      1992632.55     13907275.01
      1992672.66     13907219.23      1992675.00     13907125.00

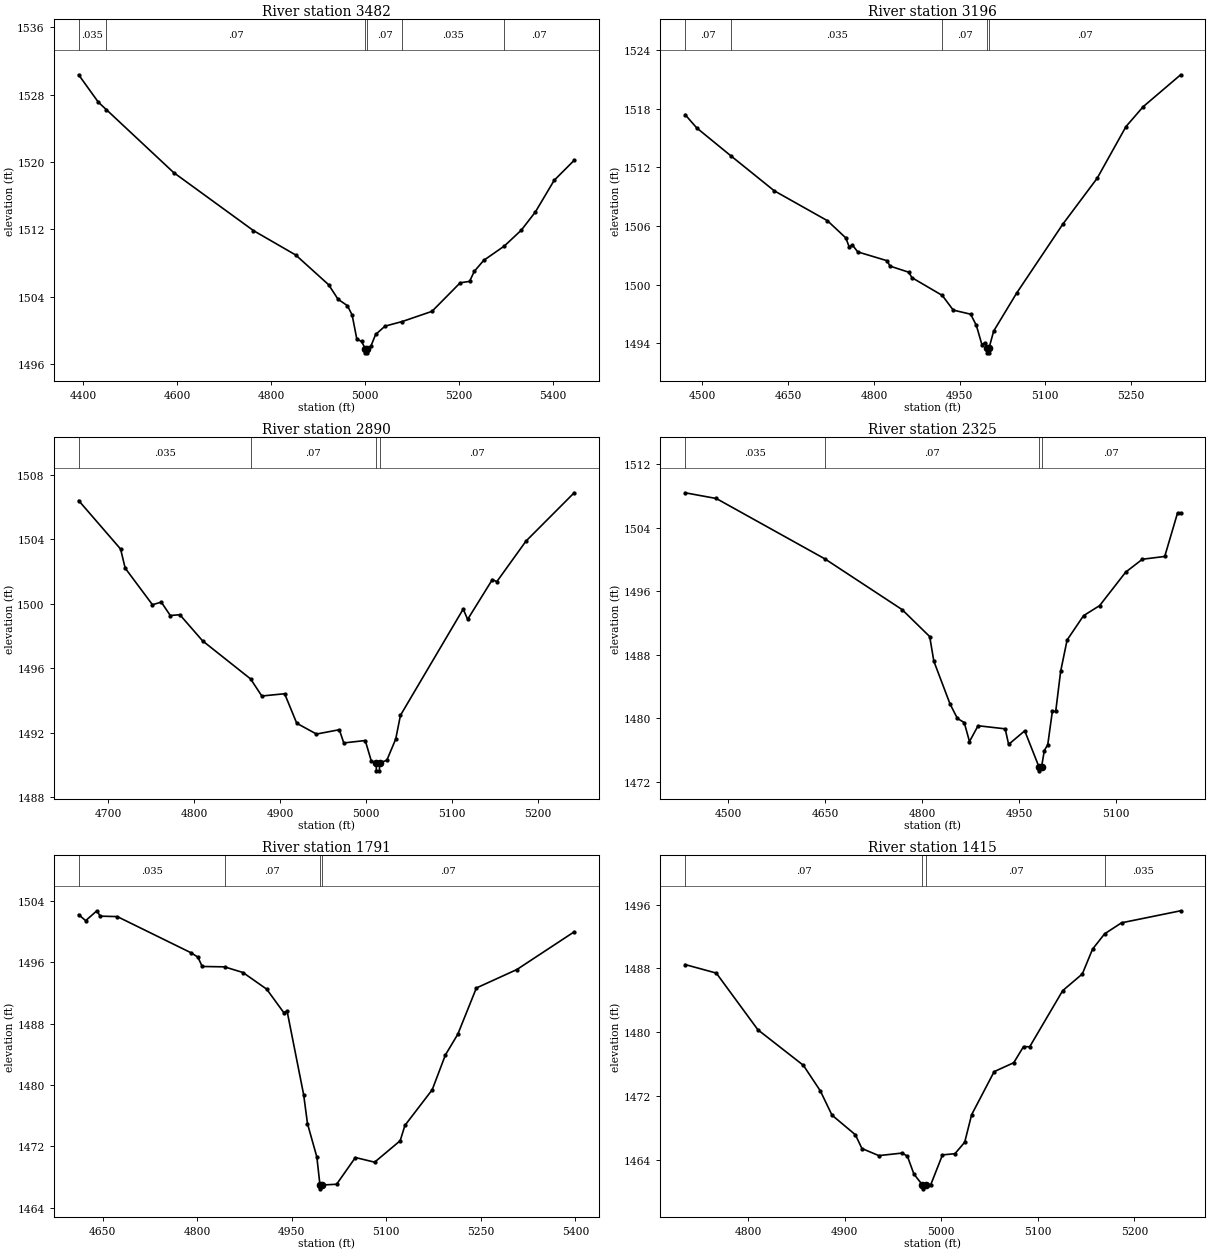
Type RM Length L Ch R = 1,3482,286,286,286
BEGIN DESCRIPTION:
Stream0085 8.0
END DESCRIPTION:
XS GIS Cut Line= 2
      1992567.05     13909953.44      1991512.37     13909961.25
#Sta/Elev= 30
  4390.6 1530.36  4432.6 1527.10  4449.6 1526.22  4592.7 1518.75  4762.7 1511.85
  4852.7 1508.95  4922.7 1505.42  4942.7 1503.70  4962.7 1502.93  4972.7 1501.83
  4982.7 1498.96  4992.7 1498.68  5000.7 1497.83  5000.9 1497.33  5004.4 1497.33
  5004.7 1497.83  5012.7 1498.13  5022.7 1499.51  5042.7 1500.50  5079.4 1501.05
  5142.7 1502.26  5202.7 1505.65  5222.7 1505.82  5232.7 1507.01  5252.7 1508.31
  5296.7 1510.02  5332.7 1511.90  5362.7 1514.06  5402.7 1517.82  5445.3 1520.20
#Mann=6,-1,0
  4390.6   0.035       0  4449.6    0.07       0  5000.7    0.05       0
  5004.7    0.07       0  5079.4   0.035       0  5296.7    0.07       0
Bank Sta=5000.7,5004.7
Exp/Cntr=0.3,0.1

Type RM Length L Ch R = 1,3196,306,306,306
BEGIN DESCRIPTION:
Stream0085 7.0
END DESCRIPTION:
XS GIS Cut Line= 3
      1992384.39     13909842.95      1991926.62     13909705.34
      1991539.96     13909660.18
#Sta/Elev= 30
  4469.6 1517.38  4489.9 1516.02  4550.2 1513.14  4625.6 1509.59  4718.7 1506.53
  4750.9 1504.77  4756.9 1503.83  4762.2 1504.06  4771.8 1503.34  4823.0 1502.44
  4828.2 1501.89  4861.2 1501.26  4866.5 1500.71  4919.7 1498.89  4938.9 1497.39
  4969.4 1496.97  4979.4 1495.82  4989.0 1493.87  4994.1 1494.06  4997.6 1493.52
  4997.8 1493.02  5001.3 1493.02  5001.6 1493.52  5009.7 1495.25  5049.9 1499.13
  5130.5 1506.16  5190.9 1510.88  5241.2 1516.15  5271.4 1518.19  5336.9 1521.45
#Mann=5,-1,0
  4469.6    0.07       0  4550.2   0.035       0  4919.7    0.07       0
  4997.6    0.05       0  5001.6    0.07       0
Bank Sta=4997.6,5001.6
Exp/Cntr=0.3,0.1

Type RM Length L Ch R = 1,2890,565,565,565
BEGIN DESCRIPTION:
Stream0085 6.0
END DESCRIPTION:
XS GIS Cut Line= 3
      1992326.48     13909545.22      1992008.41     13909441.01
      1991774.97     13909374.99
#Sta/Elev= 30
  4665.3 1506.39  4714.2 1503.38  4719.5 1502.20  4751.3 1499.93  4761.6 1500.09
  4772.1 1499.26  4783.2 1499.31  4809.7 1497.69  4865.6 1495.33  4878.7 1494.27
  4905.3 1494.41  4919.4 1492.58  4942.4 1491.91  4969.0 1492.18  4974.2 1491.36
  4999.2 1491.51  5006.2 1490.25  5011.9 1490.13  5012.2 1489.63  5015.7 1489.63
  5015.9 1490.13  5024.3 1490.28  5034.7 1491.60  5040.2 1493.07  5113.3 1499.66
  5118.5 1499.02  5147.3 1501.49  5152.5 1501.36  5186.4 1503.87  5242.6 1506.87
#Mann=4,-1,0
  4665.3   0.035       0  4865.6    0.07       0  5011.9    0.05       0
  5015.9    0.07       0
Bank Sta=5011.9,5015.9
Exp/Cntr=0.3,0.1

Type RM Length L Ch R = 1,2325,534,534,534
BEGIN DESCRIPTION:
Stream0085 5.0
END DESCRIPTION:
XS GIS Cut Line= 3
      1992509.00     13909175.49      1991975.00     13908975.00
      1991780.57     13908953.62
#Sta/Elev= 30
  4433.4 1508.41  4481.6 1507.69  4649.6 1500.08  4768.8 1493.70  4811.5 1490.30
  4817.9 1487.20  4842.8 1481.84  4854.3 1479.99  4864.9 1479.47  4873.0 1477.08
  4886.3 1479.07  4928.2 1478.68  4933.5 1476.72  4958.4 1478.43  4980.4 1473.89
  4980.7 1473.39  4984.4 1473.89  4988.7 1475.95  4994.0 1476.69  5001.1 1480.88
  5006.3 1480.88  5013.9 1485.91  5023.9 1489.87  5049.3 1492.93  5074.2 1494.20
  5114.5 1498.42  5140.3 1500.04  5174.8 1500.39  5194.7 1505.89  5199.4 1505.89
#Mann=4,-1,0
  4433.4   0.035       0  4649.6    0.07       0  4980.4    0.05       0
  4984.4    0.07       0
Bank Sta=4980.4,4984.4
Exp/Cntr=0.3,0.1

Type RM Length L Ch R = 1,1791,376,376,376
BEGIN DESCRIPTION:
Stream0085 4.0
END DESCRIPTION:
XS GIS Cut Line= 3
      1992695.57     13908769.36      1992326.78     13908653.19
      1991933.12     13908583.73
#Sta/Elev= 30
  4611.7 1502.24  4622.8 1501.45  4640.7 1502.74  4645.9 1502.04  4673.1 1501.98
  4790.5 1497.24  4801.0 1496.68  4807.8 1495.47  4843.2 1495.42  4872.5 1494.68
  4910.1 1492.51  4937.2 1489.45  4942.5 1489.65  4968.8 1478.73  4974.9 1474.94
  4989.7 1470.61  4994.7 1466.94  4994.9 1466.44  4998.7 1466.94  5021.1 1467.04
  5050.9 1470.53  5081.4 1469.92  5122.0 1472.72  5129.5 1474.72  5172.8 1479.37
  5193.8 1483.93  5213.4 1486.62  5242.9 1492.66  5307.2 1495.07  5398.1 1499.99
#Mann=4,-1,0
  4611.7   0.035       0  4843.2    0.07       0  4994.7    0.05       0
  4998.7    0.07       0
Bank Sta=4994.7,4998.7
Exp/Cntr=0.3,0.1

Type RM Length L Ch R = 1,1415,454,454,454
BEGIN DESCRIPTION:
Stream0085 3.0
END DESCRIPTION:
XS GIS Cut Line= 3
      1992524.98     13908424.99      1992275.00     13908325.00
      1992034.64     13908283.83
#Sta/Elev= 30
  4734.8 1488.47  4767.1 1487.40  4810.2 1480.28  4857.3 1475.82  4874.8 1472.62
  4886.9 1469.57  4911.1 1467.11  4917.9 1465.38  4935.4 1464.49  4959.6 1464.81
  4965.0 1464.41  4971.7 1462.18  4980.5 1460.82  4980.7 1460.32  4984.5 1460.82
  4989.2 1460.85  5001.3 1464.58  5014.2 1464.73  5024.3 1466.17  5031.5 1469.63
  5054.8 1475.03  5075.1 1476.15  5085.2 1478.17  5091.6 1478.15  5125.8 1485.20
  5146.1 1487.29  5156.7 1490.41  5169.2 1492.33  5186.7 1493.71  5247.9 1495.22
#Mann=4,-1,0
  4734.8    0.07       0  4980.5    0.05       0  4984.5    0.07       0
  5169.2   0.035       0
Bank Sta=4980.5,4984.5
Exp/Cntr=0.3,0.1

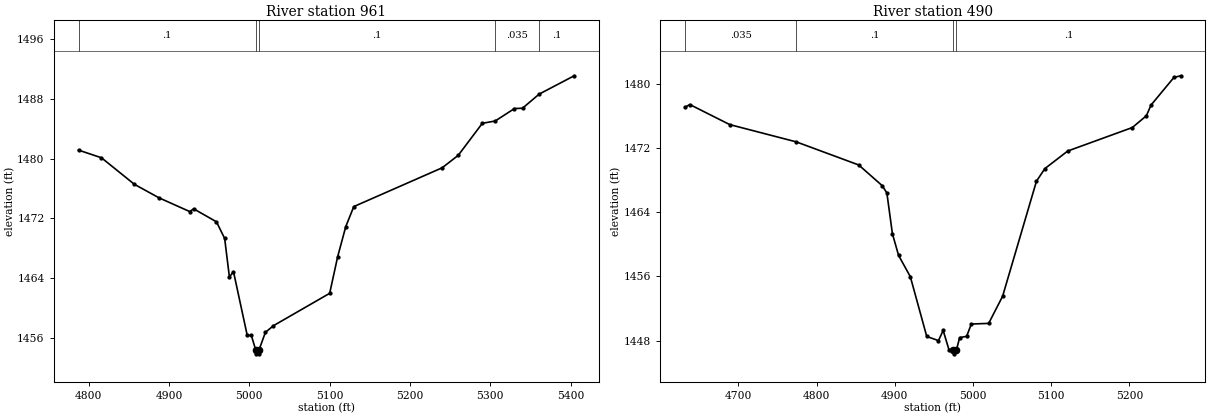
Type RM Length L Ch R = 1,961,471,471,471
BEGIN DESCRIPTION:
Stream0085 2.0
END DESCRIPTION:
XS GIS Cut Line= 3
      1992632.93     13907969.34      1992425.00     13907925.00
      1992020.72     13907920.97
#Sta/Elev= 30
  4787.5 1481.13  4816.1 1480.10  4857.0 1476.55  4887.6 1474.74  4925.8 1472.90
  4930.9 1473.26  4959.2 1471.52  4969.4 1469.29  4975.3 1464.13  4980.4 1464.84
  4997.5 1456.30  5002.6 1456.30  5008.1 1454.33  5008.4 1453.83  5011.9 1453.83
  5012.1 1454.33  5020.1 1456.71  5030.1 1457.60  5100.1 1461.94  5110.1 1466.87
  5120.1 1470.87  5130.1 1473.56  5240.1 1478.76  5260.1 1480.43  5290.1 1484.72
  5306.1 1485.03  5330.1 1486.70  5340.1 1486.74  5360.8 1488.63  5404.4 1491.09
#Mann=5,-1,0
  4787.5     0.1       0  5008.1    0.05       0  5012.1     0.1       0
  5306.1   0.035       0  5360.8     0.1       0
Bank Sta=5008.1,5012.1
Exp/Cntr=0.3,0.1

Type RM Length L Ch R = 1,490,0,0,0
BEGIN DESCRIPTION:
Stream0085 1.0
END DESCRIPTION:
XS GIS Cut Line= 3
      1992733.41     13907835.24      1992525.00     13907525.00
      1992284.54     13907425.69
#Sta/Elev= 30
  4631.7 1477.11  4637.9 1477.45  4688.9 1474.95  4774.1 1472.79  4853.9 1469.91
  4883.9 1467.33  4889.9 1466.42  4897.0 1461.32  4904.9 1458.62  4919.9 1455.97
  4940.9 1448.51  4955.9 1447.99  4961.9 1449.26  4969.3 1446.86  4974.9 1446.84
  4975.2 1446.34  4978.9 1446.84  4983.0 1448.37  4991.9 1448.52  4997.9 1450.06
  5020.1 1450.14  5037.9 1453.52  5081.2 1467.88  5091.9 1469.45  5121.2 1471.65
  5203.8 1474.58  5221.8 1476.05  5227.7 1477.38  5257.0 1480.83  5265.6 1481.04
#Mann=4,-1,0
  4631.7   0.035       0  4774.1     0.1       0  4974.9    0.05       0
  4978.9     0.1       0
Bank Sta=4974.9,4978.9
Exp/Cntr=0.3,0.1

Chan Stop Cuts=-1