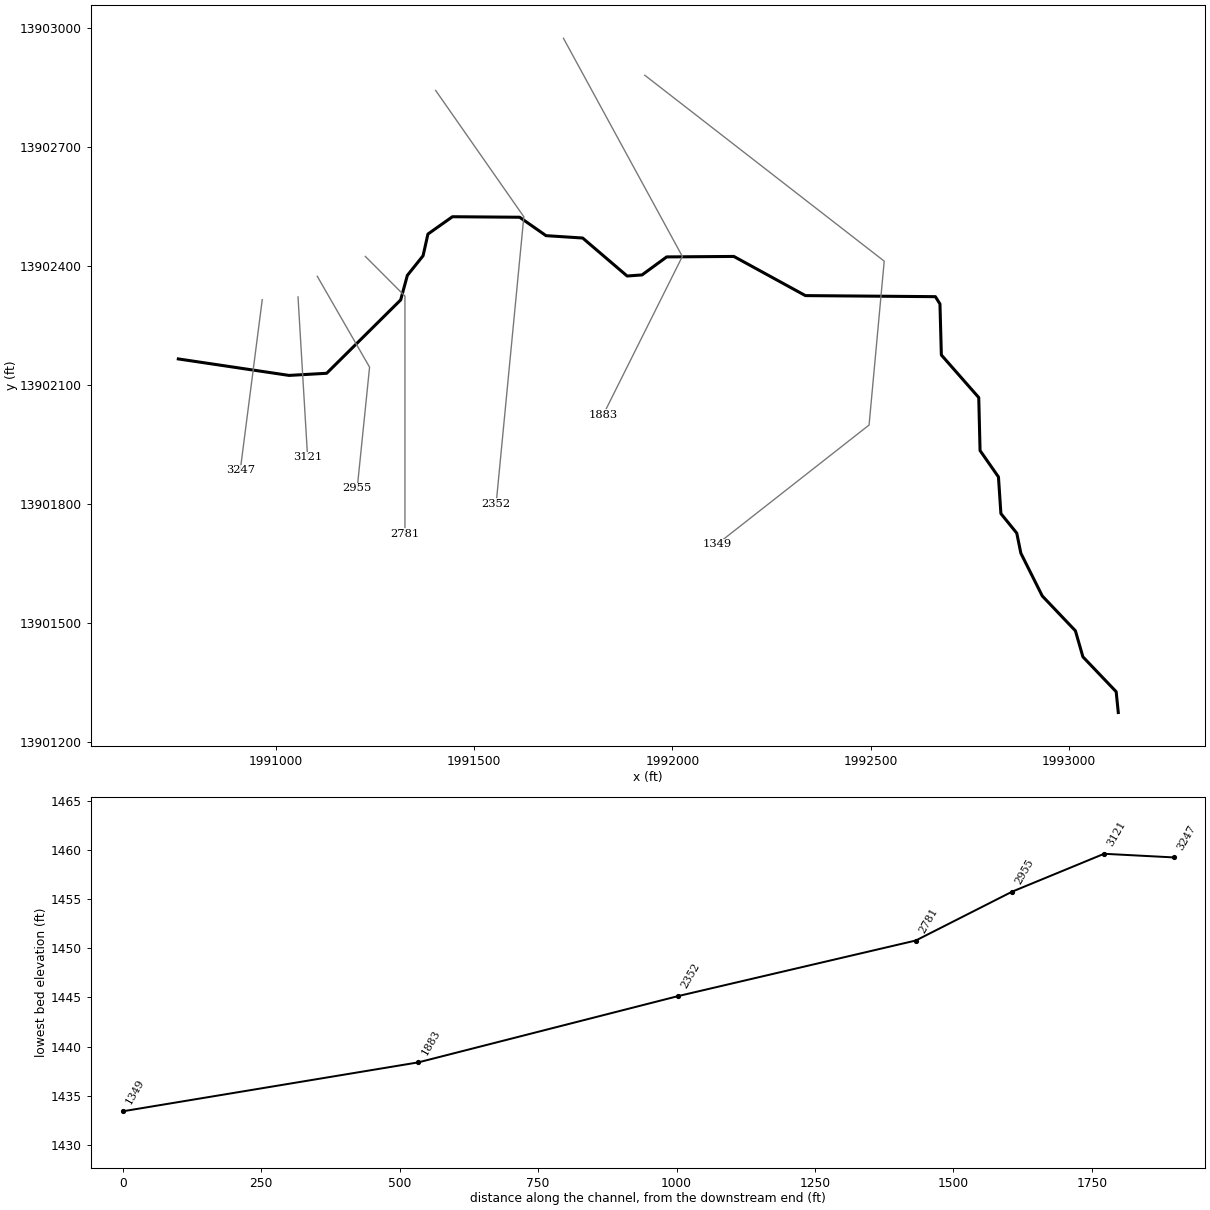
--- Stream0086.prj (project) ---

Proj Title=Stream0086 Base Level Engineering
Current Plan=p01
Default Exp/Contr=0.3,0.1
English Units
Geom File=g01
Flow File=f01
Plan File=p01
BEGIN DESCRIPTION:
Stream0086
END DESCRIPTION:

--- Stream0086.p01 (plan) ---

Plan Title=Multiple Run
Short Identifier=Multiple
Geom File=g01
Flow File=f01
Subcritical Flow
K Sum by GR= 0
Std Step Tol= 0.01
Critical Tol= 0.01
Num of Std Step Trials= 20
Max Error Tol= 0.3
Flow Tol Ratio= 0.001
Split Flow NTrial= 30
Split Flow Tol= 0.02
Split Flow Ratio= 0.02
Log Output Level= 0
Friction Slope Method= 1
Unsteady Friction Slope Method= 2
Unsteady Bridges Friction Slope Method= 1
Parabolic Critical Depth
Global Vel Dist=  1 , 1 , 1
Global Log Level= 0
CheckData=True
Encroach Param= -1, 0, 0, 0
BEGIN DESCRIPTION:
Multiple Run
END DESCRIPTION:

--- Stream0086.f01 (steady flow) ---

Flow Title=Multiple
Number of Profiles=7
Profile Names=10-year,25-year,50-year,1pct_min,100-year,1pct_plu,500-year
River Rch & RM= Stream0086,Reach-1,3247
     464     745     998     650    1297    2588    2163
Boundary for River Rch & Prof#=Stream0086,Reach-1,1
Up Type=0
Dn Type=3
Dn Slope=0.005
Boundary for River Rch & Prof#=Stream0086,Reach-1,2
Up Type=0
Dn Type=3
Dn Slope=0.005
Boundary for River Rch & Prof#=Stream0086,Reach-1,3
Up Type=0
Dn Type=3
Dn Slope=0.005
Boundary for River Rch & Prof#=Stream0086,Reach-1,4
Up Type=0
Dn Type=3
Dn Slope=0.005
Boundary for River Rch & Prof#=Stream0086,Reach-1,5
Up Type=0
Dn Type=3
Dn Slope=0.005
Boundary for River Rch & Prof#=Stream0086,Reach-1,6
Up Type=0
Dn Type=3
Dn Slope=0.005
Boundary for River Rch & Prof#=Stream0086,Reach-1,7
Up Type=0
Dn Type=3
Dn Slope=0.005

--- Stream0086.g01 (geometry) ---

Geom Title=Existing Conditions

River Reach=Stream0086,Reach-1
Reach XY= 30
      1990753.12     13902166.54      1991032.67     13902124.96
      1991127.50     13902130.35      1991314.24     13902315.32
      1991331.10     13902377.19      1991370.80     13902426.77
      1991383.00     13902481.39      1991444.88     13902525.09
      1991614.50     13902523.78      1991680.98     13902477.36
      1991773.50     13902471.38      1991885.62     13902375.60
      1991923.25     13902378.34      1991985.50     13902423.76
      1992154.97     13902424.94      1992335.50     13902326.20
      1992663.51     13902323.52      1992675.04     13902305.05
      1992678.56     13902176.48      1992772.92     13902069.14
      1992776.23     13901935.51      1992822.64     13901869.02
      1992828.83     13901776.58      1992868.88     13901727.18
      1992879.16     13901676.72      1992933.16     13901568.95
      1993016.82     13901481.04      1993035.78     13901415.32
      1993119.67     13901327.51      1993125.00     13901275.00

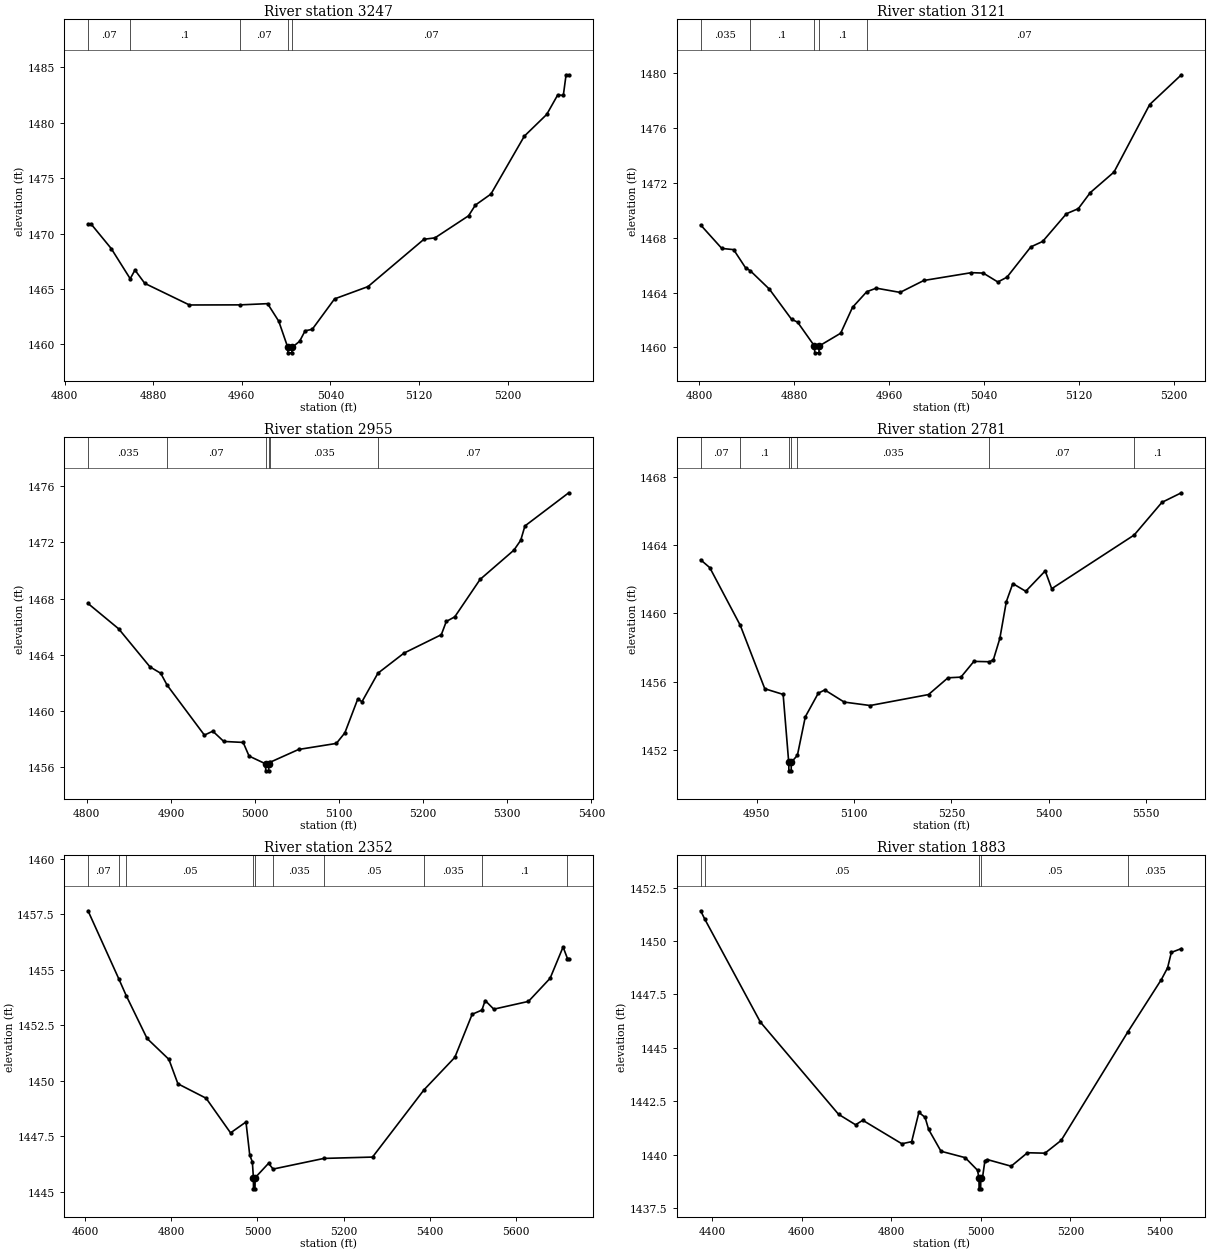
Type RM Length L Ch R = 1,3247,126,126,126
BEGIN DESCRIPTION:
Stream0086 6.0
END DESCRIPTION:
XS GIS Cut Line= 2
      1990964.92     13902315.87      1990909.36     13901885.24
#Sta/Elev= 30
  4821.1 1470.84  4824.1 1470.84  4842.1 1468.65  4859.2 1465.93  4863.5 1466.71
  4872.4 1465.51  4912.7 1463.56  4958.7 1463.57  4983.3 1463.68  4993.4 1462.09
  5001.5 1459.74  5001.7 1459.24  5005.2 1459.24  5005.5 1459.74  5012.2 1460.28
  5017.2 1461.23  5023.6 1461.36  5043.8 1464.11  5074.0 1465.22  5124.5 1469.49
  5134.5 1469.62  5164.8 1471.61  5171.0 1472.58  5185.0 1473.57  5215.2 1478.80
  5235.4 1480.76  5245.4 1482.53  5250.4 1482.47  5252.9 1484.34  5255.3 1484.34
#Mann=5,-1,0
  4821.1    0.07       0  4859.2     0.1       0  4958.7    0.07       0
  5001.5    0.05       0  5005.5    0.07       0
Bank Sta=5001.5,5005.5
Exp/Cntr=0.3,0.1

Type RM Length L Ch R = 1,3121,166,166,166
BEGIN DESCRIPTION:
Stream0086 5.0
END DESCRIPTION:
XS GIS Cut Line= 2
      1991055.20     13902322.77      1991079.40     13901918.30
#Sta/Elev= 30
  4801.3 1468.94  4819.1 1467.23  4829.1 1467.14  4839.1 1465.82  4843.0 1465.61
  4859.2 1464.26  4877.9 1462.06  4883.0 1461.85  4897.2 1460.11  4897.5 1459.61
  4901.0 1459.61  4901.2 1460.11  4919.3 1461.04  4929.3 1462.93  4941.3 1464.07
  4949.3 1464.33  4969.4 1464.02  4989.4 1464.89  5029.5 1465.46  5039.5 1465.43
  5051.8 1464.78  5059.5 1465.13  5079.6 1467.34  5089.6 1467.74  5109.6 1469.76
  5119.6 1470.13  5129.7 1471.30  5149.7 1472.80  5179.8 1477.73  5206.5 1479.90
#Mann=5,-1,0
  4801.3   0.035       0  4843.0     0.1       0  4897.2    0.05       0
  4901.2     0.1       0  4941.3    0.07       0
Bank Sta=4897.2,4901.2
Exp/Cntr=0.3,0.1

Type RM Length L Ch R = 1,2955,174,174,174
BEGIN DESCRIPTION:
Stream0086 4.0
END DESCRIPTION:
XS GIS Cut Line= 3
      1991103.80     13902374.89      1991235.75     13902145.71
      1991204.51     13901840.16
#Sta/Elev= 30
  4801.4 1467.66  4837.8 1465.86  4875.1 1463.15  4887.8 1462.70  4895.5 1461.85
  4939.8 1458.30  4949.8 1458.58  4962.8 1457.85  4985.9 1457.78  4992.9 1456.81
  5012.5 1456.26  5012.7 1455.76  5016.2 1455.76  5016.5 1456.26  5017.5 1456.36
  5051.8 1457.28  5096.7 1457.71  5106.8 1458.46  5122.1 1460.86  5127.2 1460.68
  5146.1 1462.70  5177.1 1464.13  5221.5 1465.44  5227.4 1466.38  5237.5 1466.71
  5267.6 1469.37  5307.8 1471.45  5315.9 1472.15  5320.9 1473.17  5373.0 1475.53
#Mann=6,-1,0
  4801.4   0.035       0  4895.5    0.07       0  5012.5    0.05       0
  5016.5    0.07       0  5017.5   0.035       0  5146.1    0.07       0
Bank Sta=5012.5,5016.5
Exp/Cntr=0.3,0.1

Type RM Length L Ch R = 1,2781,429,429,429
BEGIN DESCRIPTION:
Stream0086 3.0
END DESCRIPTION:
XS GIS Cut Line= 3
      1991225.03     13902424.97      1991325.00     13902325.00
      1991325.00     13901724.97
#Sta/Elev= 30
  4863.4 1463.13  4877.5 1462.67  4924.6 1459.29  4962.3 1455.59  4990.6 1455.26
  4999.2 1451.29  4999.5 1450.79  5003.0 1450.79  5003.2 1451.29  5012.6 1451.70
  5024.8 1453.95  5044.8 1455.33  5054.8 1455.52  5084.8 1454.81  5124.8 1454.61
  5214.8 1455.25  5244.8 1456.23  5264.8 1456.27  5284.8 1457.19  5308.7 1457.17
  5314.8 1457.28  5324.8 1458.53  5334.8 1460.68  5344.8 1461.74  5364.8 1461.29
  5394.8 1462.48  5404.8 1461.44  5532.0 1464.58  5574.8 1466.49  5604.8 1467.05
#Mann=7,-1,0
  4863.4    0.07       0  4924.6     0.1       0  4999.2    0.05       0
  5003.2     0.1       0  5012.6   0.035       0  5308.7    0.07       0
  5532.0     0.1       0
Bank Sta=4999.2,5003.2
Exp/Cntr=0.3,0.1

Type RM Length L Ch R = 1,2352,469,469,469
BEGIN DESCRIPTION:
Stream0086 2.0
END DESCRIPTION:
XS GIS Cut Line= 3
      1991402.44     13902843.59      1991625.00     13902525.00
      1991555.20     13901801.99
#Sta/Elev= 30
  4607.0 1457.66  4678.3 1454.60  4695.6 1453.84  4744.0 1451.91  4794.6 1450.97
  4815.5 1449.87  4880.9 1449.22  4937.6 1447.66  4973.4 1448.15  4982.1 1446.66
  4988.2 1446.35  4990.6 1445.64  4990.8 1445.14  4994.3 1445.14  4994.6 1445.64
  5025.8 1446.29  5036.3 1446.03  5154.2 1446.51  5266.9 1446.57  5386.4 1449.60
  5457.8 1451.06  5498.0 1453.00  5520.7 1453.19  5528.1 1453.62  5548.2 1453.23
  5628.6 1453.58  5678.8 1454.62  5708.9 1456.03  5719.0 1455.51  5722.0 1455.51
#Mann=10,-1,0
  4607.0    0.07       0  4678.3     0.1       0  4695.6    0.05       0
  4990.6    0.05       0  4994.6    0.05       0  5036.3   0.035       0
  5154.2    0.05       0  5386.4   0.035       0  5520.7     0.1       0
  5719.0   0.035       0
Bank Sta=4990.6,4994.6
Exp/Cntr=0.3,0.1

Type RM Length L Ch R = 1,1883,534,534,534
BEGIN DESCRIPTION:
Stream0086 1.0
END DESCRIPTION:
XS GIS Cut Line= 3
      1991725.02     13902974.97      1992025.00     13902425.00
      1991824.99     13902024.98
#Sta/Elev= 30
  4374.0 1451.42  4382.9 1451.04  4507.3 1446.21  4682.0 1441.89  4720.0 1441.40
  4736.1 1441.61  4823.4 1440.51  4845.3 1440.61  4861.4 1441.98  4875.2 1441.75
  4883.2 1441.18  4910.8 1440.16  4964.9 1439.86  4992.4 1439.27  4995.6 1438.90
  4995.9 1438.40  4999.4 1438.40  4999.6 1438.90  5003.3 1438.90  5008.8 1439.70
  5014.4 1439.77  5067.5 1439.46  5103.9 1440.09  5143.0 1440.07  5179.3 1440.67
  5328.5 1445.76  5403.0 1448.20  5416.9 1448.75  5425.3 1449.47  5447.7 1449.65
#Mann=5,-1,0
  4374.0   0.035       0  4382.9    0.05       0  4995.6    0.05       0
  4999.6    0.05       0  5328.5   0.035       0
Bank Sta=4995.6,4999.6
Exp/Cntr=0.3,0.1

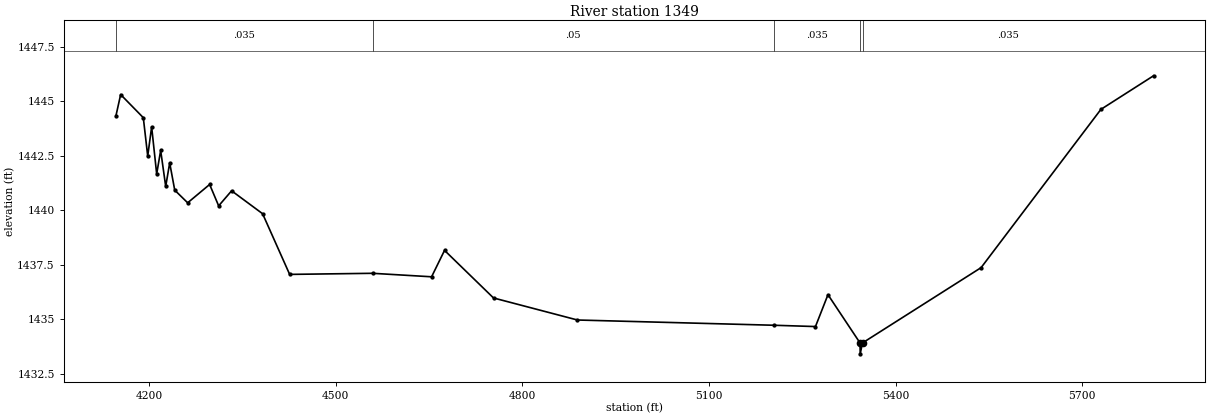
Type RM Length L Ch R = 1,1349,0,0,0
BEGIN DESCRIPTION:
Stream0086 0.0
END DESCRIPTION:
XS GIS Cut Line= 4
      1991930.19     13902881.83      1992534.37     13902413.07
      1992496.17     13901999.87      1992112.13     13901698.87
#Sta/Elev= 30
  4146.9 1444.31  4154.6 1445.30  4191.0 1444.24  4198.1 1442.48  4204.4 1443.82
  4212.5 1441.66  4218.9 1442.74  4227.0 1441.09  4233.4 1442.17  4241.5 1440.92
  4262.3 1440.34  4297.6 1441.18  4312.1 1440.20  4332.9 1440.89  4382.7 1439.84
  4426.2 1437.06  4559.5 1437.11  4654.3 1436.95  4675.1 1438.16  4753.8 1435.98
  4888.7 1434.97  5203.9 1434.73  5271.2 1434.67  5291.3 1436.13  5342.8 1433.92
  5343.1 1433.42  5346.8 1433.92  5537.4 1437.37  5729.9 1444.62  5814.5 1446.16
#Mann=5,-1,0
  4146.9   0.035       0  4559.5    0.05       0  5203.9   0.035       0
  5342.8    0.05       0  5346.8   0.035       0
Bank Sta=5342.8,5346.8
Exp/Cntr=0.3,0.1

Chan Stop Cuts=-1