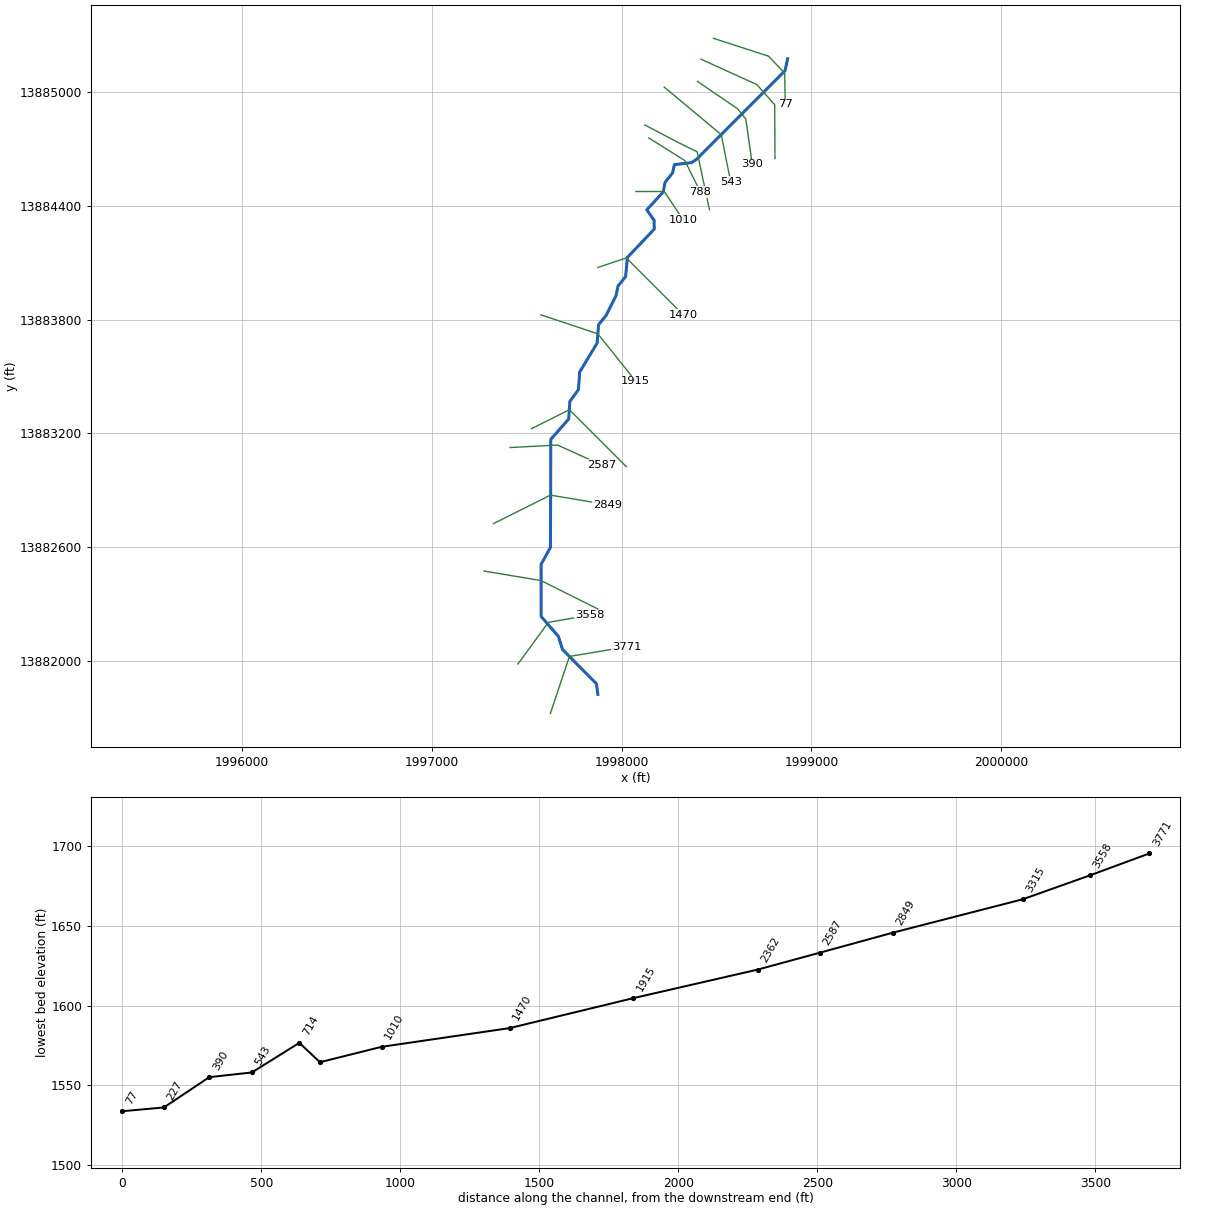
--- Stream0087.prj (project) ---

Proj Title=Stream0087 Base Level Engineering
Current Plan=p01
Default Exp/Contr=0.3,0.1
English Units
Geom File=g01
Flow File=f01
Plan File=p01
Y Axis Title=Elevation
X Axis Title(PF)=Main Channel Distance
X Axis Title(XS)=Station
BEGIN DESCRIPTION:
Stream0087
END DESCRIPTION:
DSS Export Rating Curves= 0
DSS Export Rating Curve Sorted= 0
DSS Export Volume Flow Curves= 0
DXF OffsetX= 0
DXF OffsetY= 0
DXF ScaleX= 1
DXF ScaleY= 10

--- Stream0087.p01 (plan) ---

Plan Title=Multiple Run
Short Identifier=Multiple
Geom File=g01
Flow File=f01
Subcritical Flow
K Sum by GR= 0
Std Step Tol= 0.01
Critical Tol= 0.01
Num of Std Step Trials= 20
Max Error Tol= 0.3
Flow Tol Ratio= 0.001
Split Flow NTrial= 30
Split Flow Tol= 0.02
Split Flow Ratio= 0.02
Log Output Level= 0
Friction Slope Method= 1
Unsteady Friction Slope Method= 2
Unsteady Bridges Friction Slope Method= 1
Parabolic Critical Depth
Global Vel Dist=  1 , 1 , 1
Global Log Level= 0
CheckData=True
Encroach Param= -1, 0, 0, 0
BEGIN DESCRIPTION:
Multiple Run
END DESCRIPTION:

--- Stream0087.f01 (steady flow) ---

Flow Title=Multiple
Program Version=4.10
Number of Profiles= 7
Profile Names=10-year,25-year,50-year,1pct_min,100-year,1pct_plu,500-year
River Rch & RM=Stream0087,Reach-1         ,3771
     112     163     205     126     252     503     375
River Rch & RM=Stream0087,Reach-1         ,3315
     606    1008    1385     927    1850    3692    3257
Boundary for River Rch & Prof#=Stream0087,Reach-1         , 1
Up Type= 0
Dn Type= 3
Dn Slope=0.005
Boundary for River Rch & Prof#=Stream0087,Reach-1         , 2
Up Type= 0
Dn Type= 3
Dn Slope=0.005
Boundary for River Rch & Prof#=Stream0087,Reach-1         , 3
Up Type= 0
Dn Type= 3
Dn Slope=0.005
Boundary for River Rch & Prof#=Stream0087,Reach-1         , 4
Up Type= 0
Dn Type= 3
Dn Slope=0.005
Boundary for River Rch & Prof#=Stream0087,Reach-1         , 5
Up Type= 0
Dn Type= 3
Dn Slope=0.005
Boundary for River Rch & Prof#=Stream0087,Reach-1         , 6
Up Type= 0
Dn Type= 3
Dn Slope=0.005
Boundary for River Rch & Prof#=Stream0087,Reach-1         , 7
Up Type= 0
Dn Type= 3
Dn Slope=0.005
DSS Import GetInterval= 0
DSS Import GetPeak= 0
DSS Import FillOption= 0

--- Stream0087.g01 (geometry) ---

Geom Title=Existing Conditions
Program Version=4.10

River Reach=Stream0087      ,Reach-1
Reach XY= 30
        1997875.       13881825.      1997867.24     13881881.21
      1997688.63     13882061.79      1997666.82     13882131.04
      1997576.05     13882235.44      1997575.52     13882509.78
       1997625.2     13882599.92      1997627.07     13883169.14
      1997721.38      13883276.5      1997727.36     13883369.02
      1997772.65     13883430.97      1997778.83     13883523.42
      1997871.17     13883676.58      1997878.83     13883773.42
      1997918.88     13883822.82      1997970.84     13883926.72
      1997981.12     13883977.18      1998021.17     13884026.59
      1998030.52     13884127.43      1998171.84     13884276.65
      1998171.41     13884323.35      1998132.83      13884378.4
      1998219.14      13884472.7      1998229.17      13884523.3
      1998268.74      13884573.2      1998278.38     13884616.85
      1998369.02     13884627.19      1998395.13     13884644.63
      1998861.53     13885111.73        1998875.       13885175.

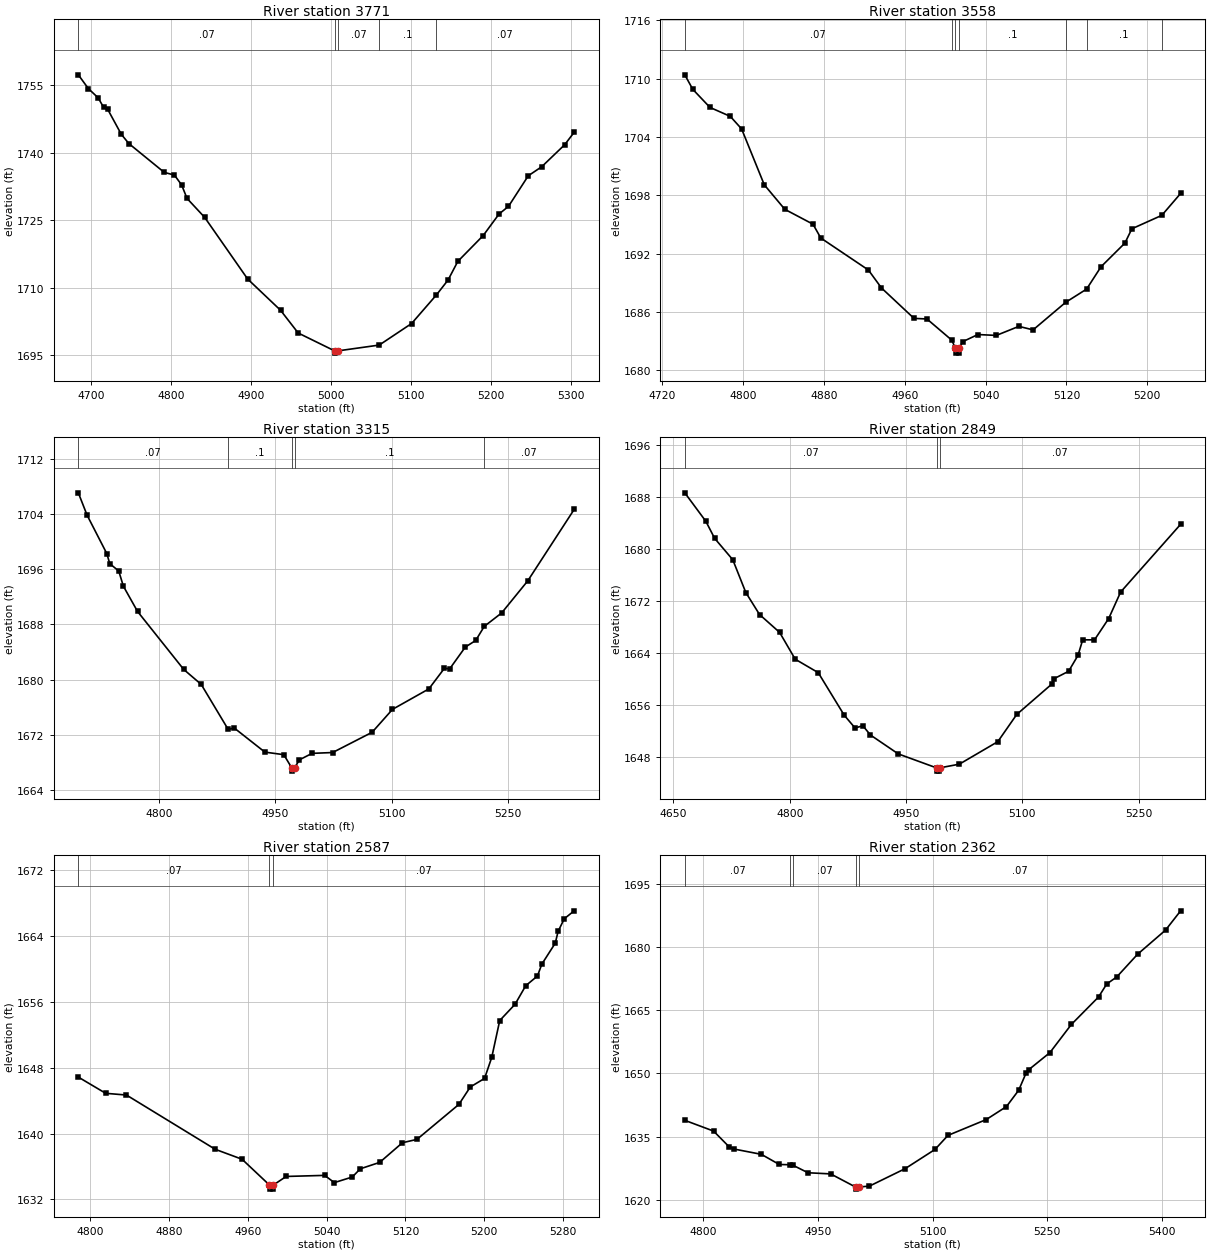
Type RM Length L Ch R = 1 ,3771    ,213,213,213
BEGIN DESCRIPTION:
Stream0087 8.0
END DESCRIPTION:
XS GIS Cut Line= 3
      1997624.99     13881724.98        1997725.       13882025.
      1998025.01       13882075.
#Sta/Elev= 30
    4684 1757.35  4696.6 1754.28  4708.8 1752.24  4715.6 1750.13  4720.7  1749.7
  4737.7 1744.15  4747.2 1742.08  4791.5 1735.67  4804.2 1735.08  4813.2  1732.9
    4820 1729.89  4842.1 1725.67  4895.9 1711.97    4937 1705.04  4959.1 1699.98
  5004.7 1696.01    5005 1695.51  5008.7 1696.01  5060.5  1697.3    5101 1702.09
    5132 1708.43  5146.6 1711.75  5158.8 1715.89  5190.6 1721.64  5210.5 1726.44
  5222.2 1728.11    5247 1734.92  5263.9 1736.94  5292.5 1741.81  5304.4 1744.58
#Mann= 5 ,-1 , 0
    4684     .07       0  5004.7     .05       0  5008.7     .07       0
  5060.5      .1       0    5132     .07       0
Bank Sta=5004.7,5008.7
XS Rating Curve= 0 ,0
Exp/Cntr=0.3,0.1

Type RM Length L Ch R = 1 ,3558    ,243,243,243
BEGIN DESCRIPTION:
Mapping XS de055d8c
END DESCRIPTION:
XS GIS Cut Line= 3
      1997454.02     13881985.61      1997614.21     13882204.78
      1997829.91      13882242.2
#Sta/Elev= 30
  4742.5 1710.38  4750.4 1708.89  4767.4 1707.03  4787.5 1706.11  4798.7 1704.82
  4821.1 1699.08  4841.4 1696.56  4869.3 1695.03    4877 1693.61  4924.1 1690.32
    4937 1688.48  4969.2 1685.35    4982 1685.29  5006.6 1683.11  5010.1 1682.28
  5010.4 1681.78  5013.9 1681.78  5014.1 1682.28  5017.2 1682.95  5032.4 1683.69
  5050.6  1683.6  5072.9 1684.53    5087 1684.17  5119.2    1687  5139.9 1688.36
  5154.2 1690.66  5177.8 1693.09  5184.7 1694.56  5214.3 1695.94  5232.9 1698.19
#Mann= 7 ,-1 , 0
  4742.5     .07       0  5006.6      .1       0  5010.1     .05       0
  5014.1      .1       0  5119.2     .07       0  5139.9      .1       0
  5214.3     .07       0
Bank Sta=5010.1,5014.1
XS Rating Curve= 0 ,0
Exp/Cntr=0.3,0.1

Type RM Length L Ch R = 1 ,3315    ,466,466,466
BEGIN DESCRIPTION:
Stream0087 7.0
END DESCRIPTION:
XS GIS Cut Line= 3
      1997275.05     13882474.99        1997575.       13882425.
        1997875.       13882275.
#Sta/Elev= 30
    4696 1707.11  4707.3 1703.86  4732.8 1698.27  4736.5 1696.83  4748.1 1695.76
  4754.1 1693.55  4772.4 1689.88  4831.9 1681.47  4854.5 1679.29  4889.3 1672.75
  4897.1 1672.96  4936.6 1669.46    4961 1669.09  4971.1  1667.2  4971.4  1666.7
  4975.1  1667.2  4981.1 1668.34  4997.5 1669.28    5024  1669.4  5074.9 1672.34
  5101.2 1675.67  5148.1 1678.64  5168.2 1681.64  5174.9 1681.54  5195.1 1684.71
  5208.5 1685.67  5219.6 1687.72    5242 1689.67  5275.6 1694.32  5335.5  1704.7
#Mann= 5 ,-1 , 0
    4696     .07       0  4889.3      .1       0  4971.1     .05       0
  4975.1      .1       0  5219.6     .07       0
Bank Sta=4971.1,4975.1
XS Rating Curve= 0 ,0
Exp/Cntr=0.3,0.1

Type RM Length L Ch R = 1 ,2849    ,262,262,262
BEGIN DESCRIPTION:
Stream0087 6.0
END DESCRIPTION:
XS GIS Cut Line= 3
      1997325.01       13882725.        1997625.       13882875.
      1997924.96     13882825.01
#Sta/Elev= 30
  4664.6 1688.58  4691.7 1684.21  4703.1 1681.58  4726.5 1678.29  4743.3 1673.25
    4761 1669.87  4786.9 1667.12    4807    1663  4836.7 1660.93  4870.2 1654.39
  4884.2 1652.42  4894.2 1652.77  4904.1 1651.34  4939.9 1648.44  4989.3 1646.29
  4989.6 1645.79  4993.1 1645.79  4993.3 1646.29  5018.7 1646.86  5068.3 1650.32
  5092.7  1654.5  5138.3 1659.21  5141.3 1660.03  5159.6 1661.14  5171.7 1663.58
  5177.8 1665.98    5193 1665.97  5211.3 1669.25  5226.7 1673.32  5304.1 1683.74
#Mann= 3 ,-1 , 0
  4664.6     .07       0  4989.3     .05       0  4993.3     .07       0
Bank Sta=4989.3,4993.3
XS Rating Curve= 0 ,0
Exp/Cntr=0.3,0.1

Type RM Length L Ch R = 1 ,2587    ,225,225,225
BEGIN DESCRIPTION:
Mapping XS def02232
END DESCRIPTION:
XS GIS Cut Line= 3
      1997412.62      13883125.8      1997662.21      13883139.1
      1997893.26     13883034.43
#Sta/Elev= 30
  4787.8 1646.86  4815.6 1644.89  4836.7 1644.68  4926.8 1638.09  4954.1 1636.88
  4981.9 1633.75  4982.1 1633.25  4985.6 1633.25  4985.9 1633.75  4998.9 1634.79
    5038 1634.92  5047.8 1634.04    5066 1634.72  5074.2 1635.72  5093.9  1636.5
    5117 1638.89  5131.7 1639.29  5174.3 1643.54  5185.9 1645.66  5200.4  1646.7
  5207.7 1649.26  5215.8 1653.73  5231.4 1655.71  5242.2 1657.96  5254.1 1659.14
  5258.6 1660.59  5272.2 1663.13  5275.1 1664.56  5281.3 1666.09  5291.4 1667.06
#Mann= 3 ,-1 , 0
  4787.8     .07       0  4981.9     .05       0  4985.9     .07       0
Bank Sta=4981.9,4985.9
XS Rating Curve= 0 ,0
Exp/Cntr=0.3,0.1

Type RM Length L Ch R = 1 ,2362    ,447,447,447
BEGIN DESCRIPTION:
Stream0087 5.0
END DESCRIPTION:
XS GIS Cut Line= 3
      1997524.96     13883224.98        1997725.       13883325.
      1998024.99     13883025.01
#Sta/Elev= 30
  4776.3 1638.88  4813.9 1636.33    4834 1632.64  4840.7 1632.07  4876.3 1630.82
  4899.8 1628.41    4914 1628.35  4918.2 1628.18  4937.3 1626.45  4966.9 1626.18
  4999.4 1623.07  4999.7 1622.57  5003.4 1623.07  5017.5 1623.28  5064.2 1627.42
  5103.2 1631.97  5120.2 1635.31  5170.2 1639.06  5196.6 1642.14  5212.6 1646.01
    5222 1649.99  5225.8 1650.89  5253.4 1654.93  5281.4  1661.6    5317 1668.13
  5327.6 1671.19  5340.8 1672.88  5367.9 1678.24  5404.5 1683.97  5424.2 1688.54
#Mann= 5 ,-1 , 0
  4776.3     .07       0    4914      .1       0  4918.2     .07       0
  4999.4     .05       0  5003.4     .07       0
Bank Sta=4999.4,5003.4
XS Rating Curve= 0 ,0
Exp/Cntr=0.3,0.1

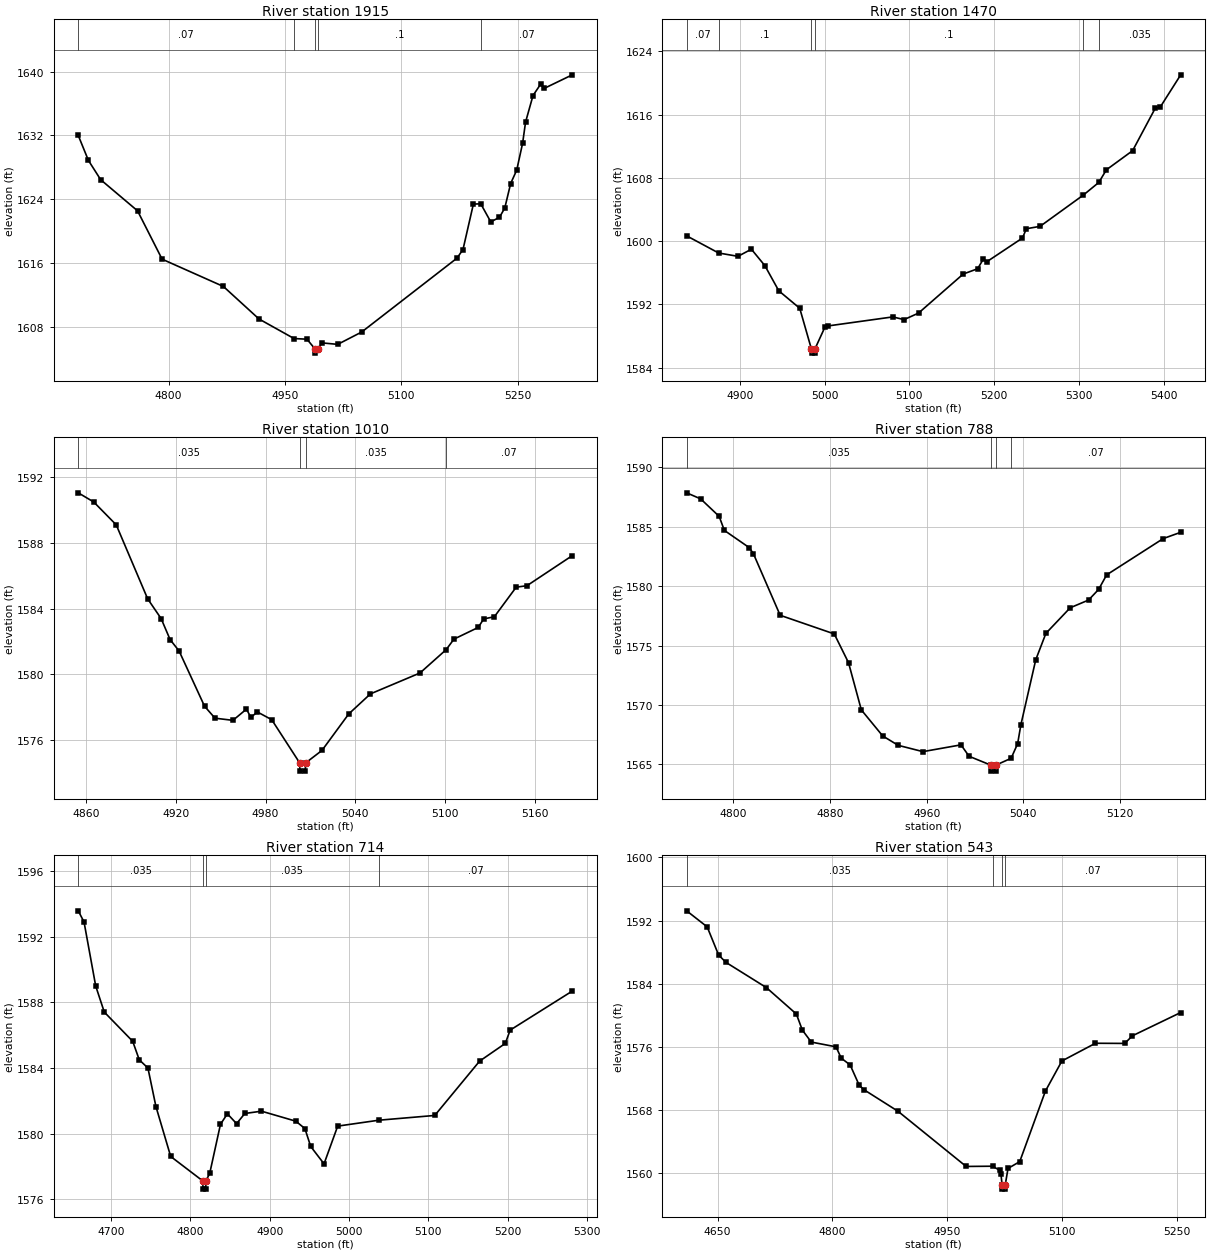
Type RM Length L Ch R = 1 ,1915    ,445,445,445
BEGIN DESCRIPTION:
Stream0087 4.0
END DESCRIPTION:
XS GIS Cut Line= 3
      1997574.96     13883825.01        1997875.       13883725.
      1998074.98     13883475.02
#Sta/Elev= 30
  4683.7    1632  4696.8 1628.86  4712.6 1626.44  4760.1 1622.53  4791.7 1616.46
  4870.7 1613.03  4916.5 1608.95  4961.7 1606.49  4978.3 1606.41  4988.9 1605.16
  4989.2 1604.66  4992.9 1605.16  4997.4 1605.95  5017.9 1605.76  5048.8 1607.31
  5171.6 1616.59  5179.3 1617.67  5192.7 1623.38  5202.2 1623.41  5215.1 1621.14
  5226.3 1621.72  5233.1 1622.87  5240.7 1625.96  5248.5 1627.64  5256.1 1631.02
  5259.9 1633.67  5269.5 1637.01  5279.2 1638.42    5284 1637.91  5320.1 1639.61
#Mann= 5 ,-1 , 0
  4683.7     .07       0  4961.7      .1       0  4988.9     .05       0
  4992.9      .1       0  5202.2     .07       0
Bank Sta=4988.9,4992.9
XS Rating Curve= 0 ,0
Exp/Cntr=0.3,0.1

Type RM Length L Ch R = 1 ,1470    ,460,460,460
BEGIN DESCRIPTION:
Stream0087 3.0
END DESCRIPTION:
XS GIS Cut Line= 3
      1997874.98     13884074.99        1998025.       13884125.
        1998325.       13883825.
#Sta/Elev= 30
  4837.5 1600.68  4875.2 1598.51    4898 1598.09  4913.8 1598.99  4929.7 1596.91
  4946.1 1593.73  4970.8 1591.52  4984.6 1586.35  4984.8 1585.85  4988.3 1585.85
  4988.6 1586.35  5000.4 1589.12  5004.2 1589.29  5080.5 1590.43  5093.8 1590.09
  5110.8 1590.91  5163.5 1595.85  5180.5 1596.52  5187.1 1597.72  5191.4 1597.41
  5233.3  1600.4    5238 1601.58  5254.1 1601.88  5305.3 1605.85  5323.3 1607.43
  5332.3 1609.03  5363.2 1611.45  5389.8  1616.8    5396    1617  5419.9 1621.04
#Mann= 6 ,-1 , 0
  4837.5     .07       0  4875.2      .1       0  4984.6     .05       0
  4988.6      .1       0  5305.3     .07       0  5323.3    .035       0
Bank Sta=4984.6,4988.6
XS Rating Curve= 0 ,0
Exp/Cntr=0.3,0.1

Type RM Length L Ch R = 1 ,1010    ,222,222,222
BEGIN DESCRIPTION:
Stream0087 2.0
END DESCRIPTION:
XS GIS Cut Line= 3
      1998075.04       13884475.        1998225.       13884475.
      1998324.98     13884325.03
#Sta/Elev= 30
  4854.8 1591.05  4865.2 1590.49  4880.2  1589.1  4901.2  1584.6  4910.2  1583.4
  4916.2 1582.12  4922.2 1581.43  4939.2 1578.07  4946.2 1577.34  4958.2 1577.21
  4967.2 1577.89  4970.2 1577.39  4974.5 1577.72  4984.1 1577.25  5002.8 1574.62
    5003 1574.12  5006.5 1574.12  5006.8 1574.62  5017.7 1575.38  5035.6  1577.6
  5050.1 1578.82  5083.2 1580.09  5100.7 1581.51  5105.9 1582.15  5122.1 1582.86
  5125.8 1583.38  5132.9 1583.51  5147.5 1585.31  5154.7  1585.4    5185 1587.23
#Mann= 4 ,-1 , 0
  4854.8    .035       0  5002.8    .035       0  5006.8    .035       0
  5100.7     .07       0
Bank Sta=5002.8,5006.8
XS Rating Curve= 0 ,0
Exp/Cntr=0.3,0.1

Type RM Length L Ch R = 1 ,788     ,74,74,74
BEGIN DESCRIPTION:
Mapping XS 41240da0
END DESCRIPTION:
XS GIS Cut Line= 3
      1998143.53     13884757.13      1998333.07     13884638.38
      1998415.34     13884472.31
#Sta/Elev= 30
  4761.3 1587.85  4772.9 1587.34  4788.2 1585.87  4792.5 1584.69  4813.1 1583.24
  4816.6 1582.72  4838.7 1577.55  4883.5 1575.98  4895.3 1573.56  4905.9 1569.59
  4923.6  1567.4  4936.4 1566.61  4956.9 1566.08  4988.4 1566.65  4995.1 1565.69
  5013.2 1564.94  5013.5 1564.44    5017 1564.44  5017.2 1564.94  5029.9 1565.52
  5035.3 1566.75    5038 1568.35  5050.3 1573.81  5058.7 1576.03  5078.8 1578.18
    5094 1578.83  5102.3 1579.72    5109 1580.95  5155.8    1584  5170.3 1584.53
#Mann= 4 ,-1 , 0
  4761.3    .035       0  5013.2    .035       0  5017.2    .035       0
  5029.9     .07       0
Bank Sta=5013.2,5017.2
XS Rating Curve= 0 ,0
Exp/Cntr=0.3,0.1

Type RM Length L Ch R = 1 ,714     ,171,171,171
BEGIN DESCRIPTION:
Stream0087 1.1
END DESCRIPTION:
XS GIS Cut Line= 4
      1998122.32     13884825.78      1998304.64     13884730.28
      1998397.95     13884684.71      1998463.06     13884378.72
#Sta/Elev= 30
  4658.8 1593.57  4666.1 1592.89  4680.8 1588.99  4691.6  1587.4  4727.4 1585.62
  4735.7 1584.49  4746.6 1583.99  4756.7 1581.64  4775.3  1578.6  4815.7 1577.11
    4816 1576.61  4819.5 1576.61  4819.7 1577.11  4824.5 1577.58    4838 1580.56
  4846.7  1581.2  4858.3  1580.6  4868.7 1581.22  4889.7 1581.36    4933 1580.75
  4944.4  1580.3  4951.7 1579.21  4968.5 1578.15  4985.7 1580.45  5037.5 1580.81
    5108  1581.1  5164.5 1584.41  5196.9 1585.49    5203  1586.3  5281.3 1588.68
#Mann= 4 ,-1 , 0
  4658.8    .035       0  4815.7    .035       0  4819.7    .035       0
  5037.5     .07       0
Bank Sta=4815.7,4819.7
XS Rating Curve= 0 ,0
Exp/Cntr=0.3,0.1

Type RM Length L Ch R = 1 ,543     ,153,153,153
BEGIN DESCRIPTION:
Stream0087 1.0
END DESCRIPTION:
XS GIS Cut Line= 3
      1998225.01     13885024.99        1998525.       13884775.
      1998574.99     13884525.05
#Sta/Elev= 30
  4609.5 1593.23  4636.3  1591.2  4651.2 1587.65  4660.6 1586.72  4713.7 1583.51
  4752.8 1580.17  4760.6 1578.14  4772.3 1576.62  4804.6 1576.02  4811.4 1574.59
  4823.1 1573.72  4834.8 1571.18  4840.8 1570.61  4885.5 1567.87  4974.6 1560.88
  5009.1 1560.91  5018.5 1560.39  5020.1 1559.89  5021.6 1558.51  5021.9 1558.01
  5025.4 1558.01  5025.6 1558.51  5029.3 1560.63  5044.6 1561.49  5078.2 1570.43
  5099.7 1574.23  5143.5 1576.47  5181.7 1576.45  5191.9 1577.42  5254.9 1580.36
#Mann= 4 ,-1 , 0
  4609.5    .035       0  5009.1     .07       0  5021.6    .035       0
  5025.6     .07       0
Bank Sta=5021.6,5025.6
XS Rating Curve= 0 ,0
Exp/Cntr=0.3,0.1

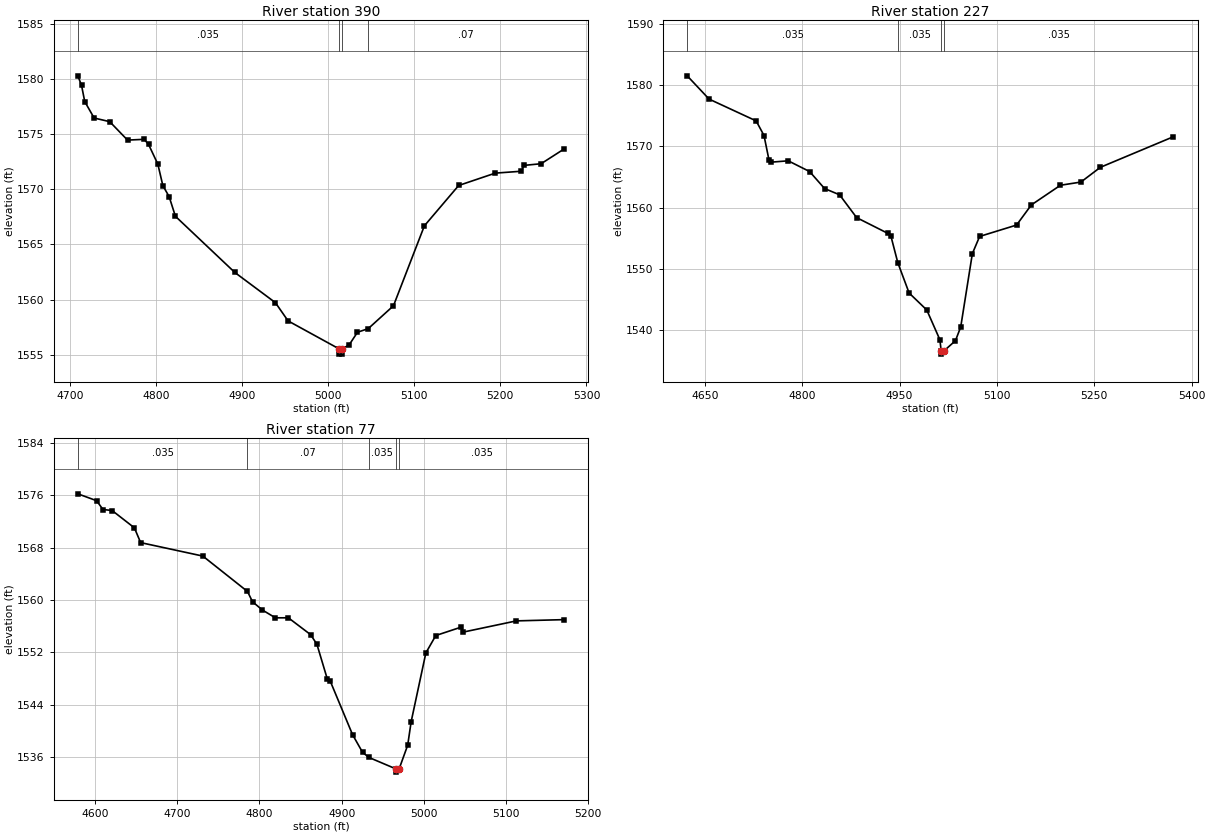
Type RM Length L Ch R = 1 ,390     ,163,163,163
BEGIN DESCRIPTION:
Mapping XS ed84b61f
END DESCRIPTION:
XS GIS Cut Line= 4
      1998400.49     13885054.76      1998612.65     13884910.14
      1998654.51     13884856.59      1998688.56     13884619.25
#Sta/Elev= 30
  4709.4 1580.27  4713.7  1579.4  4717.4 1577.94  4728.3 1576.45  4746.4 1576.12
  4767.1 1574.45  4786.4 1574.52  4791.5 1574.06  4802.3 1572.27  4808.1 1570.33
  4815.4 1569.33  4822.7 1567.55  4891.6 1562.47  4938.8 1559.73  4953.5 1558.08
  5012.2 1555.57  5012.5 1555.07    5016 1555.07  5016.2 1555.57  5024.1 1555.87
  5034.1 1557.05  5046.6 1557.38  5075.9 1559.45  5111.8 1566.69  5151.6 1570.34
  5194.1 1571.46  5224.4 1571.63  5227.4 1572.16  5247.3 1572.31  5273.9 1573.64
#Mann= 4 ,-1 , 0
  4709.4    .035       0  5012.2    .035       0  5016.2    .035       0
  5046.6     .07       0
Bank Sta=5012.2,5016.2
XS Rating Curve= 0 ,0
Exp/Cntr=0.3,0.1

Type RM Length L Ch R = 1 ,227     ,150,150,150
BEGIN DESCRIPTION:
Stream0087 0.0
END DESCRIPTION:
XS GIS Cut Line= 4
      1998418.43     13885172.31      1998712.88     13885038.47
        1998807.     13884932.29      1998808.32     13884648.82
#Sta/Elev= 30
    4623 1581.51  4656.7 1577.71  4729.2 1574.15  4741.3 1571.76  4748.9  1567.8
  4752.2 1567.41  4778.6 1567.63  4811.5 1565.88  4834.6  1563.1  4857.7 1562.08
    4884 1558.35  4932.3 1555.77  4936.8 1555.32  4947.4 1550.99  4964.8 1546.04
    4992 1543.27  5012.2 1538.41  5014.2 1536.56  5014.4 1536.06  5018.2 1536.56
  5036.2 1538.26  5044.3  1540.5  5062.2 1552.47  5073.4 1555.28  5130.3 1557.14
  5153.1 1560.43  5197.9 1563.64  5229.4 1564.16  5259.4 1566.57  5371.8 1571.56
#Mann= 4 ,-1 , 0
    4623    .035       0  4947.4    .035       0  5014.2    .035       0
  5018.2    .035       0
Bank Sta=5014.2,5018.2
XS Rating Curve= 0 ,0
Exp/Cntr=0.3,0.1

Type RM Length L Ch R = 1 ,77      ,0,0,0
BEGIN DESCRIPTION:
Stream0087 0.1
END DESCRIPTION:
XS GIS Cut Line= 4
      1998484.38     13885282.27      1998774.32     13885188.28
      1998859.69     13885098.53      1998862.18     13884935.61
#Sta/Elev= 30
    4579 1576.24  4601.8 1575.19  4609.6 1573.84  4620.7 1573.69  4647.8 1571.04
  4655.4 1568.78  4731.1 1566.72  4785.4 1561.31  4791.6 1559.73  4803.6 1558.47
  4819.4 1557.28  4835.2 1557.28  4862.2 1554.71  4869.9 1553.24  4882.5 1547.95
  4886.3 1547.55  4913.3 1539.41  4925.5  1536.7  4933.3 1535.92    4966 1534.18
  4966.2 1533.68    4970 1534.18  4980.4  1537.8  4984.6 1541.39  5002.5 1551.91
  5014.6 1554.57  5045.1 1555.84  5048.2  1555.1  5112.7 1556.81  5170.6    1557
#Mann= 5 ,-1 , 0
    4579    .035       0  4785.4     .07       0  4933.3    .035       0
    4966    .035       0    4970    .035       0
Bank Sta=4966,4970
XS Rating Curve= 0 ,0
Exp/Cntr=0.3,0.1

Chan Stop Cuts=-1
Use User Specified Reach Order=0
Composite Channel Slope=5