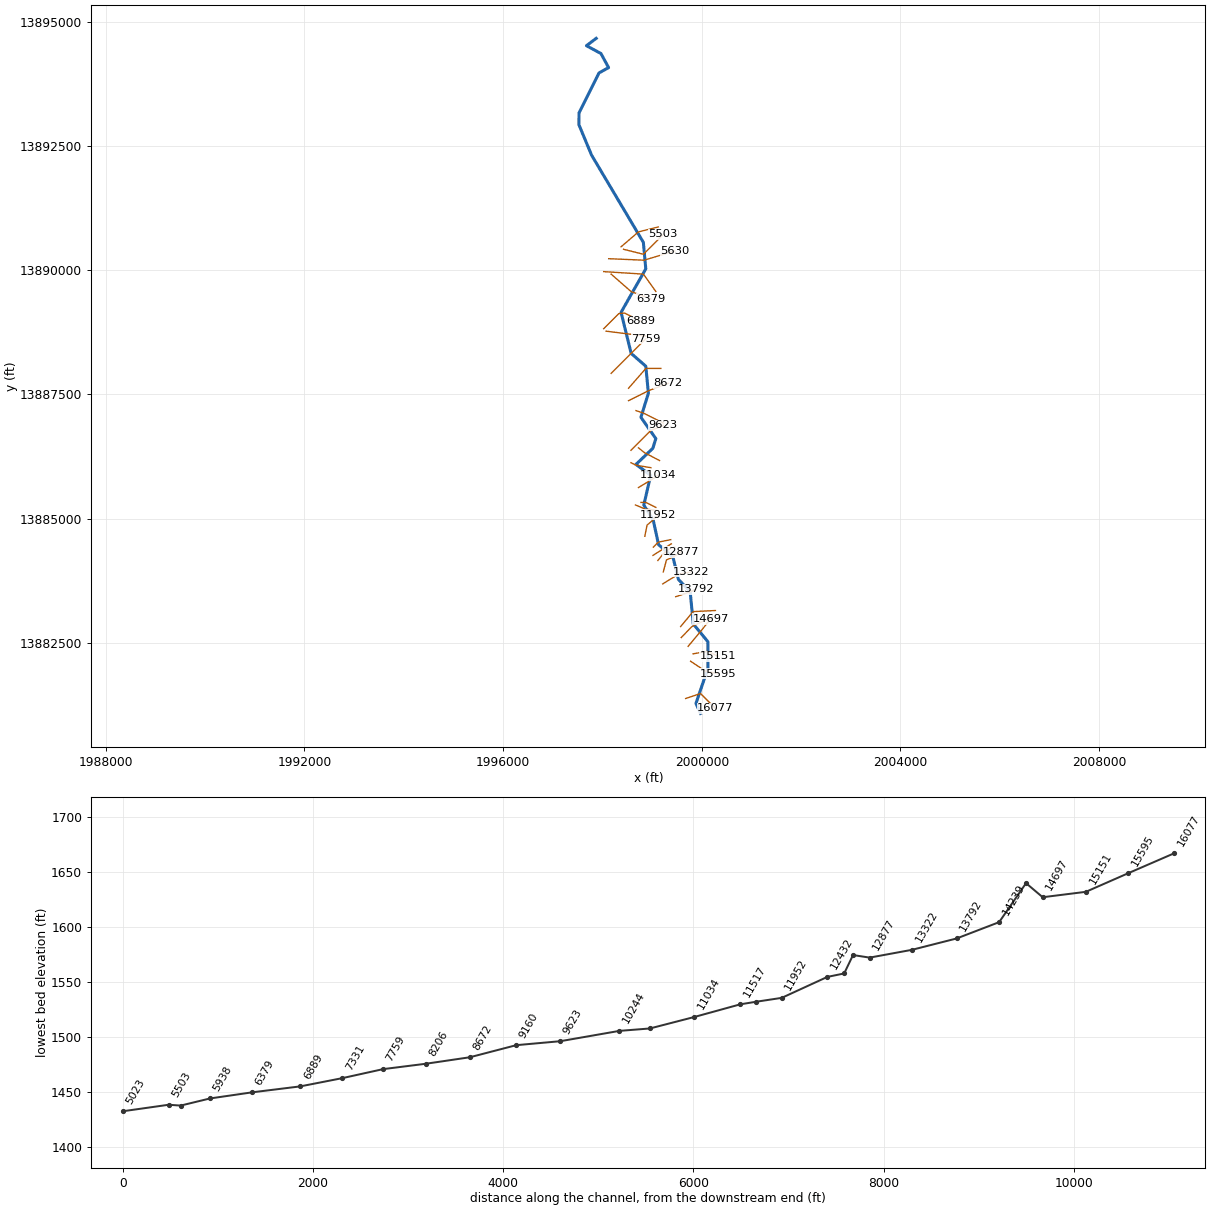
--- Stream0096.prj (project) ---

Proj Title=Stream0096 Base Level Engineering
Current Plan=p01
Default Exp/Contr=0.3,0.1
English Units
Geom File=g01
Flow File=f01
Plan File=p01
BEGIN DESCRIPTION:
Stream0096
END DESCRIPTION:

--- Stream0096.p01 (plan) ---

Plan Title=Multiple Run
Short Identifier=Multiple
Geom File=g01
Flow File=f01
Subcritical Flow
K Sum by GR= 0
Std Step Tol= 0.01
Critical Tol= 0.01
Num of Std Step Trials= 20
Max Error Tol= 0.3
Flow Tol Ratio= 0.001
Split Flow NTrial= 30
Split Flow Tol= 0.02
Split Flow Ratio= 0.02
Log Output Level= 0
Friction Slope Method= 1
Unsteady Friction Slope Method= 2
Unsteady Bridges Friction Slope Method= 1
Parabolic Critical Depth
Global Vel Dist=  1 , 1 , 1
Global Log Level= 0
CheckData=True
Encroach Param= -1, 0, 0, 0
BEGIN DESCRIPTION:
Multiple Run
END DESCRIPTION:

--- Stream0096.f01 (steady flow) ---

Flow Title=Multiple
Number of Profiles=7
Profile Names=10-year,25-year,50-year,1pct_min,100-year,1pct_plu,500-year
River Rch & RM= Stream0096,Reach-1,16077
     407     658     887     583    1164    2322    1974
River Rch & RM= Stream0096,Reach-1,15151
     785    1324    1836    1237    2469    4926    4411
River Rch & RM= Stream0096,Reach-1,11678
    1194    2064    2909    1989    3968    7917    7305
River Rch & RM= Stream0096,Reach-1,9623
    1463    2559    3634    2501    4990    9957    9315
River Rch & RM= Stream0096,Reach-1,8672
    1678    2951    4207    2904    5795   11562   10887
River Rch & RM= Stream0096,Reach-1,6379
    2018    3584    5142    3570    7123   14212   13542
River Rch & RM= Stream0096,Reach-1,5630
    2390    4272    6153    4286    8551   17062   16364
River Rch & RM= Stream0096,Reach-1,2361
    2525    4518    6513    4538    9054   18065   17338
Boundary for River Rch & Prof#=Stream0096,Reach-1,1
Up Type=0
Dn Type=3
Dn Slope=0.005
Boundary for River Rch & Prof#=Stream0096,Reach-1,2
Up Type=0
Dn Type=3
Dn Slope=0.005
Boundary for River Rch & Prof#=Stream0096,Reach-1,3
Up Type=0
Dn Type=3
Dn Slope=0.005
Boundary for River Rch & Prof#=Stream0096,Reach-1,4
Up Type=0
Dn Type=3
Dn Slope=0.005
Boundary for River Rch & Prof#=Stream0096,Reach-1,5
Up Type=0
Dn Type=3
Dn Slope=0.005
Boundary for River Rch & Prof#=Stream0096,Reach-1,6
Up Type=0
Dn Type=3
Dn Slope=0.005
Boundary for River Rch & Prof#=Stream0096,Reach-1,7
Up Type=0
Dn Type=3
Dn Slope=0.005

--- Stream0096.g01 (geometry) ---

Geom Title=Existing Conditions

River Reach=Stream0096,Reach-1
Reach XY= 30
      1999975.00     13881075.00      1999882.53     13881275.01
      2000123.81     13881985.50      2000122.94     13882519.15
      1999828.54     13882876.46      1999765.85     13883531.73
      1999530.36     13883772.30      1999417.50     13884231.05
      1999130.46     13884472.54      1999021.45     13884973.53
      1998832.77     13885271.65      1998971.55     13885873.75
      1998674.89     13886090.36      1999014.39     13886414.94
      1999074.78     13886609.79      1998775.02     13887040.41
      1998925.00     13887525.00      1998872.94     13888069.15
      1998578.61     13888326.48      1998374.70     13889154.82
      1998872.81     13890030.91      1998823.78     13890564.50
      1997780.83     13892322.70      1997526.12     13892935.46
      1997528.75     13893173.45      1997930.41     13893977.71
      1998124.14     13894085.31      1997969.38     13894369.38
      1997677.98     13894526.43      1997875.00     13894675.00

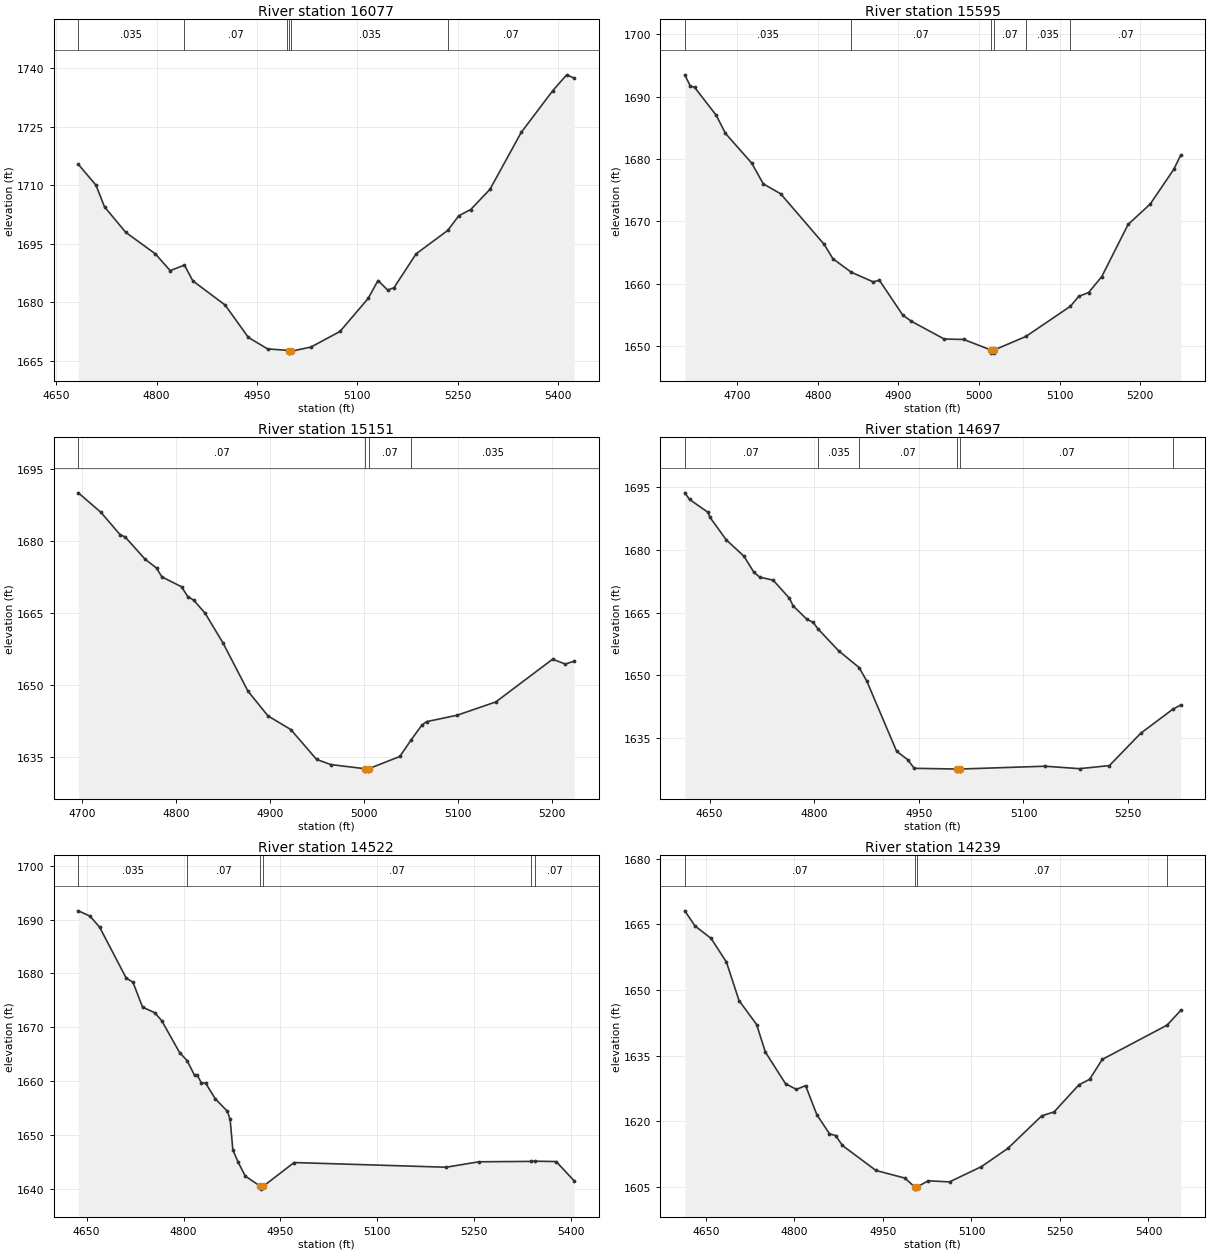
Type RM Length L Ch R = 1,16077,482,482,482
BEGIN DESCRIPTION:
Stream0096 34.0
END DESCRIPTION:
XS GIS Cut Line= 3
      1999675.00     13881375.00      1999975.00     13881475.00
      2000275.01     13881174.99
#Sta/Elev= 30
  4683.2 1715.39  4709.6 1710.03  4722.3 1704.49  4753.9 1697.96  4798.2 1692.43
  4820.3 1688.13  4841.7 1689.53  4854.2 1685.49  4902.5 1679.28  4937.2 1670.97
  4965.8 1668.04  4994.7 1667.67  4997.4 1667.45  4997.7 1666.95  5001.4 1667.45
  5030.6 1668.51  5074.0 1672.51  5116.0 1680.98  5130.8 1685.58  5145.2 1683.14
  5154.6 1683.73  5187.6 1692.42  5235.0 1698.45  5251.3 1702.19  5269.2 1703.80
  5297.9 1708.97  5344.6 1723.58  5391.7 1734.29  5412.5 1738.36  5423.7 1737.53
#Mann=6,-1,0
  4683.2   0.035       0  4841.7    0.07       0  4994.7   0.035       0
  4997.4   0.035       0  5001.4   0.035       0  5235.0    0.07       0
Bank Sta=4997.4,5001.4
Exp/Cntr=0.3,0.1

Type RM Length L Ch R = 1,15595,444,444,444
BEGIN DESCRIPTION:
Stream0096 33.0
END DESCRIPTION:
XS GIS Cut Line= 3
      1999775.03     13882124.98      2000075.00     13881925.00
      2000325.03     13881874.99
#Sta/Elev= 30
  4634.8 1693.49  4641.8 1691.65  4646.9 1691.50  4673.9 1686.99  4685.3 1684.10
  4717.8 1679.36  4732.2 1676.02  4753.8 1674.43  4807.9 1666.31  4818.7 1664.02
  4841.5 1661.86  4868.6 1660.32  4876.4 1660.57  4905.3 1655.01  4916.1 1654.00
  4956.9 1651.16  4981.0 1651.09  5014.8 1649.40  5015.1 1648.90  5018.6 1648.90
  5018.8 1649.40  5058.2 1651.57  5113.4 1656.40  5123.9 1658.00  5136.1 1658.61
  5152.4 1661.16  5185.1 1669.52  5212.6 1672.79  5241.8 1678.35  5250.3 1680.60
#Mann=6,-1,0
  4634.8   0.035       0  4841.5    0.07       0  5014.8    0.05       0
  5018.8    0.07       0  5058.2   0.035       0  5113.4    0.07       0
Bank Sta=5014.8,5018.8
Exp/Cntr=0.3,0.1

Type RM Length L Ch R = 1,15151,454,454,454
BEGIN DESCRIPTION:
Stream0096 32.0
END DESCRIPTION:
XS GIS Cut Line= 3
      1999825.02     13882275.00      2000125.00     13882325.00
      2000324.98     13882225.01
#Sta/Elev= 30
  4695.8 1690.00  4719.9 1685.93  4740.4 1681.26  4745.5 1680.84  4766.8 1676.20
  4779.0 1674.35  4784.7 1672.51  4805.6 1670.45  4812.4 1668.38  4818.5 1667.68
  4830.7 1664.96  4849.9 1658.71  4876.3 1648.74  4897.6 1643.58  4921.9 1640.74
  4949.3 1634.53  4964.4 1633.45  5000.8 1632.58  5001.0 1632.08  5004.5 1632.08
  5004.8 1632.58  5038.0 1635.13  5050.2 1638.64  5061.5 1641.68  5066.4 1642.38
  5098.9 1643.71  5140.2 1646.49  5200.6 1655.38  5214.0 1654.37  5223.5 1654.95
#Mann=4,-1,0
  4695.8    0.07       0  5000.8    0.05       0  5004.8    0.07       0
  5050.2   0.035       0
Bank Sta=5000.8,5004.8
Exp/Cntr=0.3,0.1

Type RM Length L Ch R = 1,14697,175,175,175
BEGIN DESCRIPTION:
Stream0096 31.0
END DESCRIPTION:
XS GIS Cut Line= 3
      1999725.03     13882425.04      1999975.00     13882725.00
      2000174.99     13882974.98
#Sta/Elev= 30
  4614.6 1693.55  4621.4 1691.97  4647.5 1688.94  4650.6 1687.73  4674.0 1682.34
  4699.5 1678.41  4713.5 1674.64  4722.0 1673.44  4741.2 1672.72  4764.6 1668.40
  4769.8 1666.59  4789.3 1663.43  4798.7 1662.63  4805.2 1661.16  4834.9 1655.90
  4864.4 1651.88  4875.4 1648.66  4918.2 1631.90  4933.8 1629.94  4943.5 1627.84
  5004.8 1627.67  5005.0 1627.17  5008.5 1627.17  5008.8 1627.67  5130.9 1628.34
  5180.3 1627.76  5223.1 1628.49  5267.8 1636.17  5314.1 1641.95  5325.2 1642.94
#Mann=6,-1,0
  4614.6    0.07       0  4805.2   0.035       0  4864.4    0.07       0
  5004.8    0.05       0  5008.8    0.07       0  5314.1   0.035       0
Bank Sta=5004.8,5008.8
Exp/Cntr=0.3,0.1

Type RM Length L Ch R = 1,14522,283,283,283
BEGIN DESCRIPTION:
Stream0096 30.1
END DESCRIPTION:
XS GIS Cut Line= 4
      1999587.16     13882603.51      1999797.69     13882820.56
      2000034.24     13882937.74      2000220.91     13883013.71
#Sta/Elev= 30
  4637.1 1691.63  4654.9 1690.67  4670.0 1688.61  4711.1 1679.17  4721.7 1678.36
  4736.6 1673.74  4755.7 1672.68  4766.3 1671.21  4793.9 1665.31  4805.6 1663.80
  4817.2 1661.05  4821.5 1661.06  4827.8 1659.63  4834.2 1659.63  4849.0 1656.74
  4868.0 1654.38  4872.2 1652.88  4876.4 1647.22  4884.8 1644.88  4895.7 1642.36
  4919.2 1640.43  4919.4 1639.93  4923.2 1640.43  4971.2 1644.87  5206.8 1644.00
  5257.5 1645.01  5337.8 1645.08  5344.7 1645.12  5377.1 1645.05  5405.0 1641.47
#Mann=6,-1,0
  4637.1   0.035       0  4805.6    0.07       0  4919.2    0.05       0
  4923.2    0.07       0  5337.8   0.035       0  5344.7    0.07       0
Bank Sta=4919.2,4923.2
Exp/Cntr=0.3,0.1

Type RM Length L Ch R = 1,14239,447,447,447
BEGIN DESCRIPTION:
Stream0096 30.0
END DESCRIPTION:
XS GIS Cut Line= 3
      1999574.99     13882824.98      1999825.00     13883125.00
      2000274.21     13883147.39
#Sta/Elev= 30
  4614.2 1668.08  4631.5 1664.63  4658.8 1661.78  4684.8 1656.37  4706.1 1647.60
  4735.9 1642.13  4750.8 1635.82  4784.9 1628.62  4803.3 1627.32  4818.9 1628.18
  4838.1 1621.51  4859.4 1617.19  4869.7 1616.78  4881.4 1614.51  4938.2 1608.81
  4987.2 1607.07  5003.8 1605.05  5004.1 1604.55  5007.8 1605.05  5026.8 1606.45
  5062.9 1606.21  5117.0 1609.69  5161.5 1613.83  5219.1 1621.28  5240.1 1622.18
  5282.2 1628.38  5300.2 1629.61  5321.7 1634.16  5431.6 1641.99  5454.5 1645.33
#Mann=4,-1,0
  4614.2    0.07       0  5003.8    0.05       0  5007.8    0.07       0
  5431.6   0.035       0
Bank Sta=5003.8,5007.8
Exp/Cntr=0.3,0.1

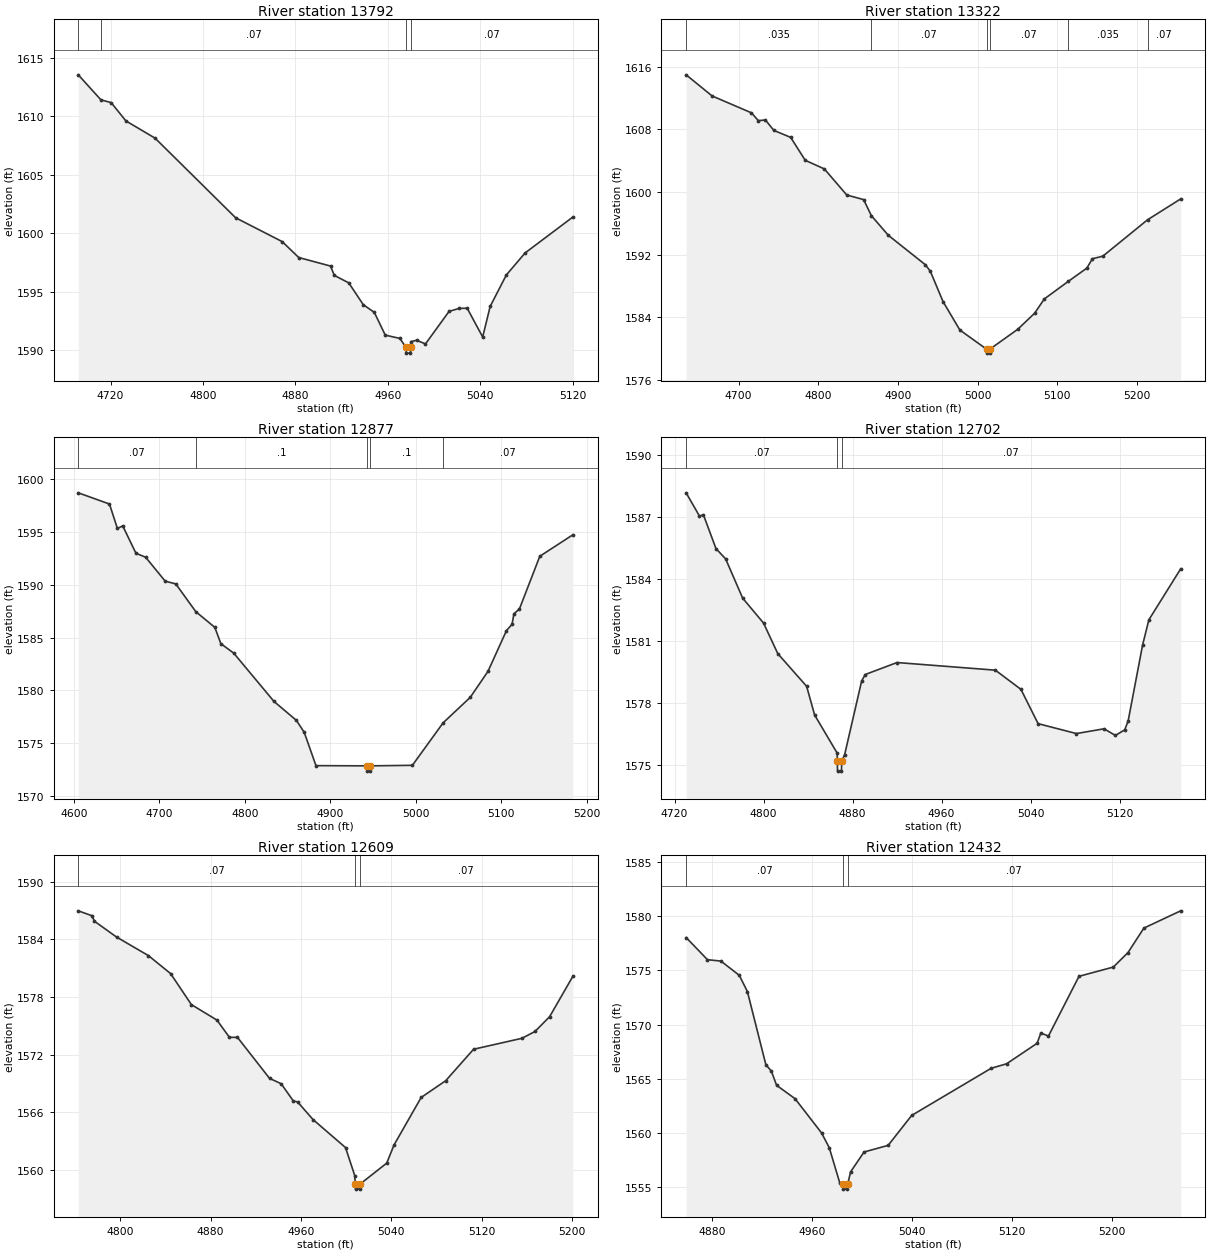
Type RM Length L Ch R = 1,13792,470,470,470
BEGIN DESCRIPTION:
Stream0096 29.0
END DESCRIPTION:
XS GIS Cut Line= 3
      1999475.03     13883425.01      1999775.00     13883525.00
      1999875.00     13883575.00
#Sta/Elev= 30
  4692.0 1613.55  4711.6 1611.41  4720.5 1611.17  4733.2 1609.61  4758.5 1608.13
  4828.2 1601.32  4868.5 1599.28  4882.8 1597.92  4910.3 1597.19  4913.6 1596.39
  4926.1 1595.75  4938.7 1593.88  4948.2 1593.23  4957.7 1591.28  4970.3 1591.00
  4975.6 1590.24  4975.9 1589.74  4979.4 1589.74  4979.6 1590.24  4979.8 1590.72
  4984.8 1590.84  4992.5 1590.53  5012.9 1593.31  5021.7 1593.57  5028.6 1593.58
  5042.0 1591.12  5048.5 1593.74  5062.5 1596.43  5078.7 1598.31  5120.0 1601.38
#Mann=4,-1,0
  4692.0   0.035       0  4711.6    0.07       0  4975.6    0.05       0
  4979.6    0.07       0
Bank Sta=4975.6,4979.6
Exp/Cntr=0.3,0.1

Type RM Length L Ch R = 1,13322,445,445,445
BEGIN DESCRIPTION:
Stream0096 28.0
END DESCRIPTION:
XS GIS Cut Line= 3
      1999213.31     13883683.35      1999525.00     13883875.00
      1999774.95     13883924.99
#Sta/Elev= 30
  4634.2 1614.98  4666.8 1612.28  4716.1 1610.13  4724.8 1609.13  4733.7 1609.21
  4744.3 1607.88  4765.4 1606.99  4783.7 1604.06  4807.7 1602.96  4835.8 1599.63
  4857.0 1599.04  4866.7 1596.99  4888.0 1594.48  4934.5 1590.72  4940.7 1589.89
  4956.7 1586.01  4977.8 1582.38  5011.4 1579.93  5011.7 1579.43  5015.2 1579.43
  5015.4 1579.93  5050.5 1582.48  5071.6 1584.52  5083.8 1586.35  5113.7 1588.58
  5137.2 1590.29  5144.2 1591.49  5157.2 1591.81  5213.5 1596.47  5255.0 1599.13
#Mann=6,-1,0
  4634.2   0.035       0  4866.7    0.07       0  5011.4    0.05       0
  5015.4    0.07       0  5113.7   0.035       0  5213.5    0.07       0
Bank Sta=5011.4,5015.4
Exp/Cntr=0.3,0.1

Type RM Length L Ch R = 1,12877,175,175,175
BEGIN DESCRIPTION:
Stream0096 27.0
END DESCRIPTION:
XS GIS Cut Line= 4
      1999225.00     13883924.99      1999289.06     13884167.39
      1999425.00     13884225.00      1999574.96     13884324.97
#Sta/Elev= 30
  4605.2 1598.73  4641.7 1597.67  4651.0 1595.35  4657.2 1595.60  4672.7 1593.00
  4684.0 1592.63  4706.9 1590.36  4719.3 1590.10  4742.7 1587.47  4765.0 1585.98
  4772.0 1584.44  4787.1 1583.54  4834.1 1578.97  4860.4 1577.17  4869.6 1576.03
  4883.3 1572.88  4943.1 1572.86  4943.3 1572.36  4946.8 1572.36  4947.1 1572.86
  4996.1 1572.91  5032.1 1576.94  5063.8 1579.35  5084.6 1581.82  5106.2 1585.68
  5112.7 1586.27  5114.9 1587.26  5121.4 1587.74  5145.2 1592.72  5183.8 1594.75
#Mann=5,-1,0
  4605.2    0.07       0  4742.7     0.1       0  4943.1    0.05       0
  4947.1     0.1       0  5032.1    0.07       0
Bank Sta=4943.1,4947.1
Exp/Cntr=0.3,0.1

Type RM Length L Ch R = 1,12702,93,93,93
BEGIN DESCRIPTION:
Stream0087 27.1
END DESCRIPTION:
XS GIS Cut Line= 4
      1999116.28     13884155.21      1999222.61     13884287.57
      1999363.67     13884400.42      1999454.77     13884424.28
#Sta/Elev= 30
  4730.4 1588.17  4742.4 1587.04  4745.9 1587.11  4757.2 1585.47  4765.9 1584.97
  4781.2 1583.07  4800.0 1581.86  4812.8 1580.38  4838.7 1578.80  4845.9 1577.41
  4866.2 1575.56  4866.3 1575.19  4866.5 1574.69  4870.0 1574.69  4870.3 1575.19
  4872.9 1575.49  4888.2 1579.06  4891.4 1579.37  4920.0 1579.95  5008.4 1579.58
  5031.4 1578.65  5046.8 1576.99  5081.2 1576.51  5106.1 1576.74  5116.3 1576.42
  5124.7 1576.69  5127.8 1577.13  5140.8 1580.81  5146.4 1582.02  5175.0 1584.49
#Mann=3,-1,0
  4730.4    0.07       0  4866.3    0.05       0  4870.3    0.07       0
Bank Sta=4866.3,4870.3
Exp/Cntr=0.3,0.1

Type RM Length L Ch R = 1,12609,177,177,177
BEGIN DESCRIPTION:
Mapping XS 9c32b49d
END DESCRIPTION:
XS GIS Cut Line= 2
      1999016.70     13884257.92      1999387.47     13884491.09
#Sta/Elev= 30
  4762.8 1586.97  4774.9 1586.46  4777.1 1585.89  4796.7 1584.24  4825.0 1582.30
  4844.6 1580.43  4863.0 1577.20  4885.6 1575.59  4896.7 1573.79  4903.8 1573.79
  4932.2 1569.52  4942.5 1568.96  4953.3 1567.16  4957.0 1567.07  4970.7 1565.23
  4999.5 1562.31  5007.7 1559.38  5008.1 1558.48  5008.4 1557.98  5011.9 1557.98
  5012.1 1558.48  5036.0 1560.69  5042.5 1562.59  5066.5 1567.53  5088.2 1569.27
  5112.9 1572.55  5155.7 1573.69  5167.3 1574.40  5180.3 1575.95  5200.8 1580.14
#Mann=3,-1,0
  4762.8    0.07       0  5008.1    0.05       0  5012.1    0.07       0
Bank Sta=5008.1,5012.1
Exp/Cntr=0.3,0.1

Type RM Length L Ch R = 1,12432,480,480,480
BEGIN DESCRIPTION:
Stream0096 26.0
END DESCRIPTION:
XS GIS Cut Line= 3
      1999024.97     13884424.97      1999125.00     13884525.00
      1999374.99     13884575.00
#Sta/Elev= 30
  4859.0 1578.01  4876.1 1575.97  4886.9 1575.84  4901.6 1574.53  4908.1 1573.03
  4922.9 1566.30  4927.3 1565.71  4931.5 1564.40  4946.3 1563.17  4967.5 1560.02
  4973.7 1558.66  4982.2 1555.39  4984.6 1555.34  4984.8 1554.84  4988.3 1554.84
  4988.6 1555.34  4990.8 1556.43  5001.6 1558.26  5020.9 1558.87  5039.8 1561.63
  5103.5 1565.97  5115.8 1566.38  5140.3 1568.27  5143.3 1569.21  5149.4 1568.94
  5173.9 1574.44  5201.4 1575.29  5213.2 1576.63  5225.9 1578.88  5255.4 1580.47
#Mann=3,-1,0
  4859.0    0.07       0  4984.6    0.05       0  4988.6    0.07       0
Bank Sta=4984.6,4988.6
Exp/Cntr=0.3,0.1

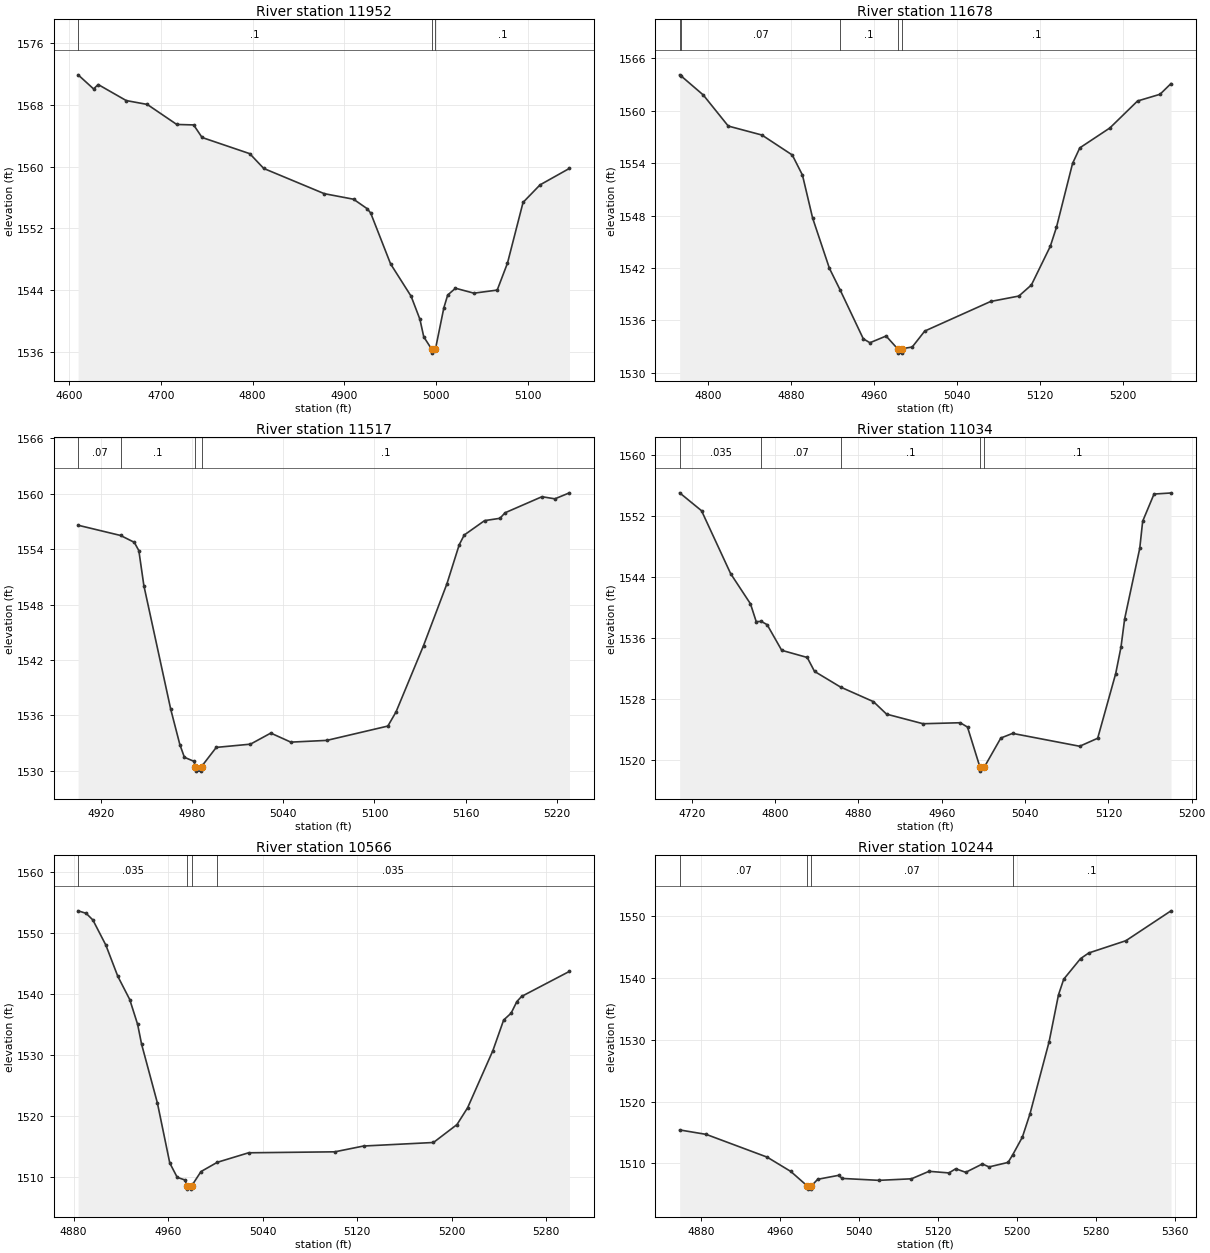
Type RM Length L Ch R = 1,11952,274,274,274
BEGIN DESCRIPTION:
Stream0096 25.0
END DESCRIPTION:
XS GIS Cut Line= 4
      1998852.55     13884643.83      1998898.31     13884867.71
      1999025.00     13884975.00      1999124.97     13885074.97
#Sta/Elev= 30
  4609.6 1571.93  4626.5 1570.10  4631.5 1570.67  4662.1 1568.59  4685.0 1568.09
  4717.2 1565.49  4735.6 1565.43  4744.8 1563.80  4796.8 1561.70  4812.1 1559.78
  4878.1 1556.51  4910.0 1555.79  4924.9 1554.56  4928.7 1554.00  4950.4 1547.40
  4972.8 1543.20  4982.4 1540.21  4986.6 1537.93  4995.3 1536.32  4995.5 1535.82
  4999.3 1536.32  5008.5 1541.70  5012.7 1543.36  5021.2 1544.24  5041.3 1543.60
  5066.7 1544.00  5077.9 1547.50  5094.9 1555.38  5113.4 1557.65  5145.5 1559.79
#Mann=3,-1,0
  4609.6     0.1       0  4995.3    0.05       0  4999.3     0.1       0
Bank Sta=4995.3,4999.3
Exp/Cntr=0.3,0.1

Type RM Length L Ch R = 1,11678,161,161,161
BEGIN DESCRIPTION:
Mapping XS 7c5ac079
END DESCRIPTION:
XS GIS Cut Line= 3
      1998663.85     13885274.12      1998852.68     13885194.68
      1999119.61     13885159.52
#Sta/Elev= 30
  4772.3 1564.12  4774.0 1563.96  4795.1 1561.81  4819.2 1558.25  4851.7 1557.22
  4881.0 1554.93  4890.8 1552.63  4900.6 1547.71  4916.8 1541.95  4927.1 1539.48
  4949.5 1533.87  4955.9 1533.42  4971.5 1534.19  4982.6 1532.73  4982.9 1532.23
  4986.4 1532.23  4986.6 1532.73  4996.7 1532.93  5008.8 1534.76  5072.4 1538.15
  5099.6 1538.77  5111.7 1540.04  5129.9 1544.46  5135.9 1546.66  5151.4 1553.96
  5158.4 1555.75  5187.4 1558.03  5214.1 1561.12  5235.8 1561.89  5246.4 1563.12
#Mann=5,-1,0
  4772.3   0.035       0  4774.0    0.07       0  4927.1     0.1       0
  4982.6    0.05       0  4986.6     0.1       0
Bank Sta=4982.6,4986.6
Exp/Cntr=0.3,0.1

Type RM Length L Ch R = 1,11517,483,483,483
BEGIN DESCRIPTION:
Stream0096 24.0
END DESCRIPTION:
XS GIS Cut Line= 3
      1998775.04     13885325.00      1998875.00     13885325.00
      1999075.03     13885224.98
#Sta/Elev= 30
  4904.8 1556.60  4932.8 1555.49  4941.8 1554.75  4944.8 1553.85  4948.1 1550.07
  4965.8 1536.67  4971.8 1532.85  4974.8 1531.47  4981.1 1531.03  4982.1 1530.47
  4982.4 1529.97  4985.9 1529.97  4986.1 1530.47  4995.8 1532.54  5018.3 1532.89
  5031.7 1534.09  5044.9 1533.11  5068.6 1533.30  5108.8 1534.85  5114.2 1536.39
  5132.3 1543.57  5147.7 1550.26  5155.8 1554.49  5159.1 1555.54  5172.5 1557.10
  5182.6 1557.35  5186.0 1557.95  5210.3 1559.69  5218.8 1559.46  5228.4 1560.11
#Mann=4,-1,0
  4904.8    0.07       0  4932.8     0.1       0  4982.1    0.05       0
  4986.1     0.1       0
Bank Sta=4982.1,4986.1
Exp/Cntr=0.3,0.1

Type RM Length L Ch R = 1,11034,468,468,468
BEGIN DESCRIPTION:
Stream0096 23.0
END DESCRIPTION:
XS GIS Cut Line= 3
      1998725.03     13885625.02      1998975.00     13885775.00
      1999125.01     13885875.01
#Sta/Elev= 30
  4708.3 1555.07  4729.3 1552.72  4757.3 1544.44  4776.3 1540.48  4781.8 1538.15
  4786.8 1538.16  4792.3 1537.74  4806.3 1534.37  4830.8 1533.43  4837.8 1531.60
  4862.8 1529.54  4894.4 1527.62  4907.0 1525.98  4942.0 1524.72  4977.7 1524.85
  4984.7 1524.28  4996.7 1518.99  4997.0 1518.49  5000.7 1518.99  5016.7 1522.84
  5028.0 1523.45  5092.4 1521.76  5109.7 1522.81  5127.0 1531.31  5132.1 1534.81
  5135.6 1538.51  5150.1 1547.78  5152.9 1551.34  5163.8 1554.91  5180.1 1555.05
#Mann=5,-1,0
  4708.3   0.035       0  4786.8    0.07       0  4862.8     0.1       0
  4996.7    0.05       0  5000.7     0.1       0
Bank Sta=4996.7,5000.7
Exp/Cntr=0.3,0.1

Type RM Length L Ch R = 1,10566,322,322,322
BEGIN DESCRIPTION:
Stream0096 22.0
END DESCRIPTION:
XS GIS Cut Line= 3
      1998575.02     13886124.99      1998675.00     13886075.00
      1998974.98     13886025.00
#Sta/Elev= 30
  4883.9 1553.70  4890.7 1553.29  4896.4 1552.20  4907.4 1548.07  4917.5 1542.96
  4927.6 1539.15  4934.3 1535.06  4937.6 1531.85  4951.0 1522.19  4961.5 1512.33
  4967.8 1509.98  4974.5 1509.54  4975.9 1508.55  4976.1 1508.05  4979.6 1508.05
  4979.9 1508.55  4987.9 1510.93  5001.7 1512.45  5028.2 1514.01  5101.2 1514.17
  5125.5 1515.12  5184.7 1515.70  5204.6 1518.64  5213.6 1521.40  5235.0 1530.78
  5244.1 1535.79  5250.4 1536.91  5255.3 1538.82  5259.3 1539.66  5299.8 1543.77
#Mann=4,-1,0
  4883.9   0.035       0  4975.9    0.05       0  4979.9   0.035       0
  5001.7   0.035       0
Bank Sta=4975.9,4979.9
Exp/Cntr=0.3,0.1

Type RM Length L Ch R = 1,10244,621,621,621
BEGIN DESCRIPTION:
Stream0096 21.0
END DESCRIPTION:
XS GIS Cut Line= 3
      1998725.01     13886424.99      1998847.30     13886326.35
      1999149.67     13886169.15
#Sta/Elev= 30
  4858.3 1515.41  4885.2 1514.69  4947.0 1511.01  4970.9 1508.70  4987.7 1506.34
  4988.0 1505.84  4991.5 1505.84  4991.7 1506.34  4998.2 1507.43  5019.4 1508.07
  5023.0 1507.57  5060.2 1507.26  5093.2 1507.51  5111.0 1508.72  5131.2 1508.46
  5138.0 1509.13  5148.2 1508.56  5165.1 1509.91  5171.8 1509.43  5191.1 1510.16
  5195.8 1511.39  5205.6 1514.25  5213.3 1518.01  5232.7 1529.68  5242.2 1537.26
  5247.5 1539.78  5264.5 1543.10  5272.9 1544.02  5310.5 1546.00  5356.2 1550.83
#Mann=4,-1,0
  4858.3    0.07       0  4987.7    0.05       0  4991.7    0.07       0
  5195.8     0.1       0
Bank Sta=4987.7,4991.7
Exp/Cntr=0.3,0.1

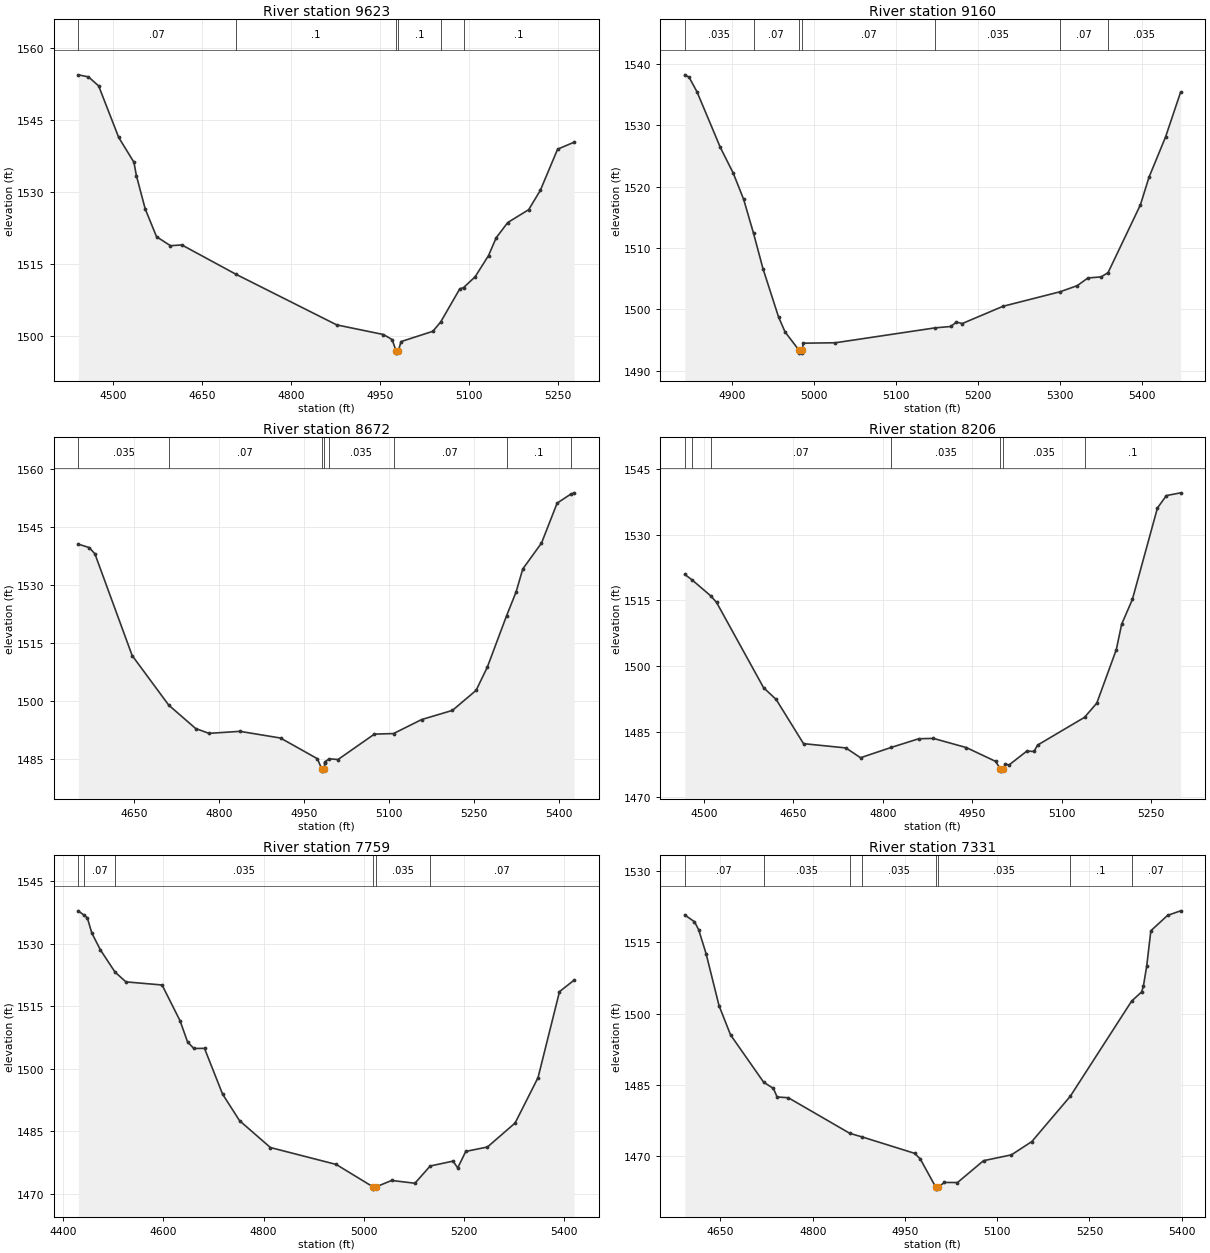
Type RM Length L Ch R = 1,9623,463,463,463
BEGIN DESCRIPTION:
Stream0096 20.0
END DESCRIPTION:
XS GIS Cut Line= 3
      1998575.02     13886375.02      1998975.00     13886775.00
      1999224.99     13886875.00
#Sta/Elev= 30
  4441.7 1554.33  4458.8 1553.90  4475.9 1552.03  4509.7 1541.31  4535.3 1536.16
  4539.5 1533.36  4554.3 1526.46  4573.4 1520.68  4596.8 1518.81  4616.0 1518.97
  4707.5 1512.85  4876.8 1502.35  4955.4 1500.35  4970.1 1499.30  4976.6 1496.98
  4976.9 1496.48  4980.6 1496.98  4985.1 1498.88  5038.7 1501.02  5052.0 1502.99
  5083.9 1509.82  5090.4 1510.11  5109.8 1512.34  5132.4 1516.76  5145.3 1520.46
  5164.7 1523.62  5200.0 1526.30  5219.6 1530.31  5248.7 1538.87  5276.6 1540.33
#Mann=6,-1,0
  4441.7    0.07       0  4707.5     0.1       0  4976.6   0.035       0
  4980.6     0.1       0  5052.0    0.07       0  5090.4     0.1       0
Bank Sta=4976.6,4980.6
Exp/Cntr=0.3,0.1

Type RM Length L Ch R = 1,9160,488,488,488
BEGIN DESCRIPTION:
Stream0096 19.0
END DESCRIPTION:
XS GIS Cut Line= 3
      1998674.98     13887175.01      1998825.00     13887125.00
      1999224.96     13886925.02
#Sta/Elev= 30
  4841.9 1538.21  4847.2 1537.81  4856.8 1535.44  4885.3 1526.38  4901.0 1522.21
  4913.8 1517.91  4925.8 1512.40  4937.3 1506.66  4956.3 1498.79  4964.3 1496.33
  4981.2 1493.38  4981.4 1492.88  4985.1 1492.88  4985.4 1493.38  4986.4 1494.50
  5025.8 1494.57  5147.7 1497.00  5166.7 1497.22  5173.4 1497.94  5180.6 1497.70
  5230.4 1500.51  5300.2 1502.88  5321.0 1503.87  5334.0 1505.12  5350.2 1505.30
  5358.6 1505.99  5398.1 1517.03  5408.6 1521.53  5428.8 1528.09  5447.2 1535.40
#Mann=7,-1,0
  4841.9   0.035       0  4925.8    0.07       0  4981.2    0.05       0
  4985.4    0.07       0  5147.7   0.035       0  5300.2    0.07       0
  5358.6   0.035       0
Bank Sta=4981.2,4985.4
Exp/Cntr=0.3,0.1

Type RM Length L Ch R = 1,8672,466,466,466
BEGIN DESCRIPTION:
Stream0096 18.0
END DESCRIPTION:
XS GIS Cut Line= 3
      1998524.99     13887374.99      1998925.00     13887575.00
      1999324.97     13887724.99
#Sta/Elev= 30
  4552.1 1540.49  4571.2 1539.62  4581.3 1538.00  4647.0 1511.75  4711.5 1498.95
  4759.0 1492.91  4782.5 1491.66  4837.1 1492.18  4908.7 1490.45  4973.7 1485.11
  4981.5 1482.41  4981.9 1481.91  4986.0 1482.41  4986.5 1483.96  4987.1 1484.29
  4994.4 1485.09  5010.1 1484.91  5074.2 1491.46  5108.0 1491.61  5157.5 1495.22
  5211.9 1497.59  5253.6 1502.76  5273.5 1508.80  5307.2 1521.97  5324.1 1528.15
  5335.9 1534.10  5368.9 1540.77  5396.5 1551.09  5420.1 1553.36  5426.5 1553.74
#Mann=8,-1,0
  4552.1   0.035       0  4711.5    0.07       0  4981.5   0.035       0
  4986.0    0.07       0  4994.4   0.035       0  5108.0    0.07       0
  5307.2     0.1       0  5420.1    0.07       0
Bank Sta=4981.5,4986
Exp/Cntr=0.3,0.1

Type RM Length L Ch R = 1,8206,447,447,447
BEGIN DESCRIPTION:
Stream0096 17.0
END DESCRIPTION:
XS GIS Cut Line= 3
      1998525.00     13887625.00      1998875.00     13888025.00
      1999175.00     13888025.00
#Sta/Elev= 30
  4468.1 1520.94  4480.7 1519.64  4511.8 1516.01  4521.4 1514.53  4600.2 1495.05
  4621.3 1492.36  4667.2 1482.26  4738.3 1481.28  4762.8 1479.04  4813.9 1481.38
  4860.4 1483.38  4885.0 1483.46  4940.3 1481.36  4989.2 1478.22  4997.4 1476.48
  4997.7 1475.98  5001.9 1476.48  5005.7 1477.64  5011.7 1477.37  5041.7 1480.56
  5053.7 1480.47  5059.7 1481.93  5138.4 1488.27  5159.0 1491.52  5191.7 1503.73
  5200.7 1509.56  5218.7 1515.22  5260.7 1536.11  5275.7 1538.95  5299.6 1539.58
#Mann=7,-1,0
  4468.1    0.07       0  4480.7   0.035       0  4511.8    0.07       0
  4813.9   0.035       0  4997.4   0.035       0  5001.9   0.035       0
  5138.4     0.1       0
Bank Sta=4997.4,5001.9
Exp/Cntr=0.3,0.1

Type RM Length L Ch R = 1,7759,428,428,428
BEGIN DESCRIPTION:
Stream0096 16.0
END DESCRIPTION:
XS GIS Cut Line= 3
      1998175.03     13887925.03      1998575.00     13888325.00
      1998874.99     13888624.99
#Sta/Elev= 30
  4430.0 1537.85  4441.9 1536.75  4447.9 1536.19  4456.9 1532.54  4473.9 1528.52
  4503.3 1523.16  4525.0 1520.82  4597.2 1520.07  4633.1 1511.49  4648.1 1506.41
  4660.6 1504.85  4681.9 1504.88  4718.0 1493.90  4751.9 1487.54  4813.5 1481.10
  4944.8 1477.05  5018.9 1471.63  5019.2 1471.13  5023.6 1471.63  5055.4 1473.21
  5102.0 1472.54  5132.4 1476.67  5178.1 1477.85  5187.4 1476.21  5203.5 1480.17
  5246.8 1481.23  5302.0 1486.98  5347.8 1497.87  5390.6 1518.47  5419.9 1521.25
#Mann=6,-1,0
  4430.0   0.035       0  4441.9    0.07       0  4503.3   0.035       0
  5018.9   0.035       0  5023.6   0.035       0  5132.4    0.07       0
Bank Sta=5018.9,5023.6
Exp/Cntr=0.3,0.1

Type RM Length L Ch R = 1,7331,442,442,442
BEGIN DESCRIPTION:
Stream0096 15.0
END DESCRIPTION:
XS GIS Cut Line= 3
      1998075.03     13888775.00      1998475.00     13888725.00
      1998875.00     13888675.00
#Sta/Elev= 30
  4592.0 1520.79  4607.7 1519.37  4614.5 1517.70  4626.6 1512.64  4647.7 1501.65
  4666.4 1495.50  4720.2 1485.52  4736.1 1484.20  4742.1 1482.40  4760.3 1482.24
  4860.3 1474.73  4880.4 1473.97  4965.8 1470.51  4974.9 1469.32  4999.7 1463.46
  5000.1 1462.96  5004.5 1463.46  5014.2 1464.37  5035.4 1464.35  5077.7 1468.96
  5123.1 1470.19  5156.3 1473.00  5218.8 1482.55  5318.5 1502.62  5334.7 1504.56
  5337.6 1505.74  5343.0 1509.97  5349.8 1517.47  5377.0 1520.71  5398.2 1521.67
#Mann=8,-1,0
  4592.0    0.07       0  4720.2   0.035       0  4860.3    0.07       0
  4880.4   0.035       0  4999.7   0.035       0  5004.5   0.035       0
  5218.8     0.1       0  5318.5    0.07       0
Bank Sta=4999.7,5004.5
Exp/Cntr=0.3,0.1

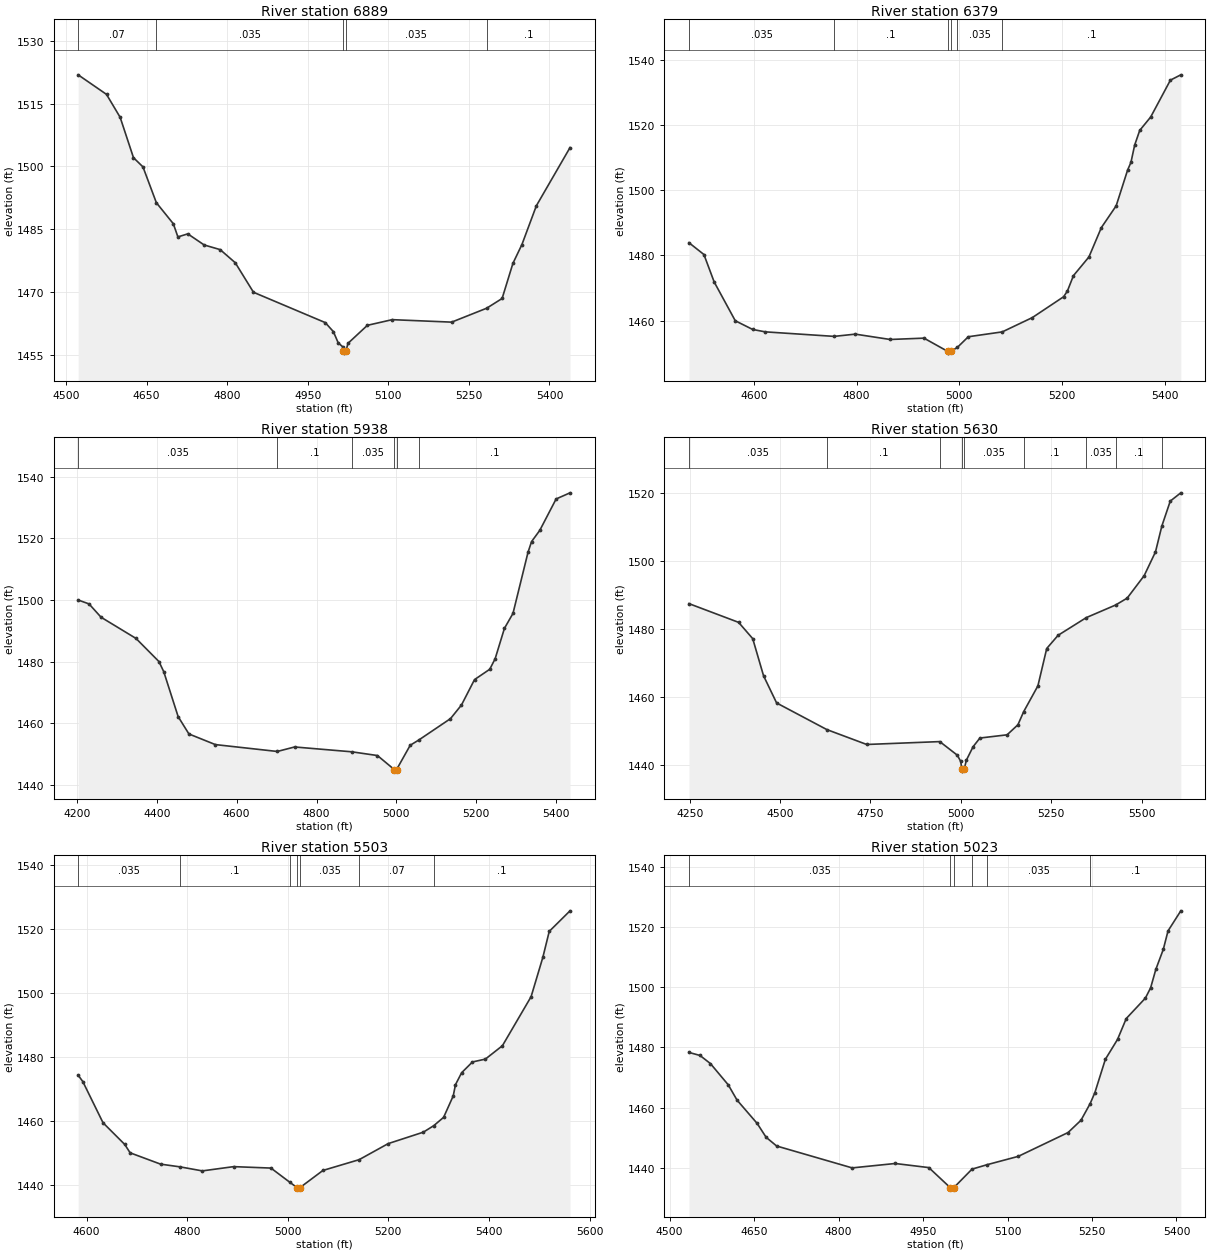
Type RM Length L Ch R = 1,6889,510,510,510
BEGIN DESCRIPTION:
Stream0096 14.0
END DESCRIPTION:
XS GIS Cut Line= 4
      1998025.00     13888825.00      1998328.86     13889128.86
      1998443.66     13889140.67      1998775.03     13888974.99
#Sta/Elev= 30
  4522.7 1521.84  4575.5 1517.18  4600.9 1511.71  4625.7 1502.09  4643.4 1499.88
  4668.3 1491.35  4699.9 1486.33  4708.4 1483.19  4726.8 1483.92  4757.3 1481.27
  4787.1 1480.16  4815.2 1477.03  4849.1 1469.99  4982.7 1462.76  4997.8 1460.61
  5006.8 1457.93  5015.9 1456.91  5016.5 1455.98  5016.8 1455.48  5021.3 1455.98
  5024.9 1457.80  5061.1 1462.11  5107.3 1463.46  5218.0 1462.87  5283.2 1466.19
  5311.9 1468.51  5332.0 1476.88  5348.8 1481.38  5375.7 1490.63  5438.3 1504.49
#Mann=5,-1,0
  4522.7    0.07       0  4668.3   0.035       0  5016.5   0.035       0
  5021.3   0.035       0  5283.2     0.1       0
Bank Sta=5016.5,5021.3
Exp/Cntr=0.3,0.1

Type RM Length L Ch R = 1,6379,441,441,441
BEGIN DESCRIPTION:
Stream0096 13.0
END DESCRIPTION:
XS GIS Cut Line= 3
      1998174.99     13889925.01      1998575.00     13889575.00
      1998974.98     13889425.01
#Sta/Elev= 30
  4473.1 1483.93  4502.3 1480.30  4522.3 1471.87  4563.4 1459.97  4597.4 1457.29
  4621.9 1456.56  4756.1 1455.17  4797.3 1455.86  4865.3 1454.22  4931.2 1454.63
  4977.9 1450.53  4978.3 1450.03  4983.5 1450.53  4996.5 1451.82  5017.6 1455.06
  5083.8 1456.55  5142.4 1460.94  5203.3 1467.33  5210.7 1469.08  5222.5 1473.81
  5252.7 1479.55  5276.9 1488.56  5305.8 1495.25  5328.2 1506.28  5334.6 1508.59
  5341.8 1513.87  5351.7 1518.40  5373.1 1522.52  5411.5 1533.83  5431.8 1535.46
#Mann=6,-1,0
  4473.1   0.035       0  4756.1     0.1       0  4977.9   0.035       0
  4983.5     0.1       0  4996.5   0.035       0  5083.8     0.1       0
Bank Sta=4977.9,4983.5
Exp/Cntr=0.3,0.1

Type RM Length L Ch R = 1,5938,308,308,308
BEGIN DESCRIPTION:
Stream0096 12.0
END DESCRIPTION:
XS GIS Cut Line= 3
      1998025.05     13889975.00      1998825.00     13889925.00
      1999074.98     13889575.02
#Sta/Elev= 30
  4203.1 1500.03  4230.4 1498.76  4260.5 1494.44  4348.0 1487.56  4405.4 1480.06
  4417.5 1476.76  4453.5 1462.19  4480.5 1456.56  4546.7 1453.11  4701.7 1450.88
  4745.1 1452.34  4888.3 1450.77  4952.5 1449.56  4994.8 1445.00  4995.2 1444.50
  5000.4 1445.00  5034.6 1452.90  5055.5 1454.55  5135.4 1461.53  5162.9 1465.95
  5195.6 1474.20  5233.7 1477.55  5247.2 1480.96  5270.5 1490.84  5291.9 1495.68
  5329.5 1515.50  5338.4 1518.98  5359.0 1522.63  5399.9 1532.82  5434.7 1534.81
#Mann=6,-1,0
  4203.1   0.035       0  4701.7     0.1       0  4888.3   0.035       0
  4994.8   0.035       0  5000.4   0.035       0  5055.5     0.1       0
Bank Sta=4994.8,5000.4
Exp/Cntr=0.3,0.1

Type RM Length L Ch R = 1,5630,127,127,127
BEGIN DESCRIPTION:
Mapping XS 14418803
END DESCRIPTION:
XS GIS Cut Line= 3
      1998125.74     13890235.55      1998837.52     13890205.17
      1999458.14     13890391.79
#Sta/Elev= 30
  4247.9 1487.46  4385.3 1481.93  4424.3 1477.13  4454.3 1466.17  4490.4 1458.16
  4629.4 1450.30  4739.6 1445.91  4941.7 1446.76  4990.1 1442.76  4999.5 1440.95
  5002.9 1438.55  5003.4 1438.05  5009.2 1438.55  5015.1 1441.25  5033.9 1445.26
  5052.7 1447.81  5127.9 1448.76  5157.8 1451.72  5173.7 1455.58  5213.1 1463.20
  5237.5 1474.22  5268.9 1478.11  5346.9 1483.33  5427.9 1487.04  5460.0 1489.08
  5507.0 1495.70  5538.3 1502.71  5555.9 1510.34  5579.2 1517.70  5608.4 1520.14
#Mann=9,-1,0
  4247.9   0.035       0  4629.4     0.1       0  4941.7   0.035       0
  5002.9   0.035       0  5009.2   0.035       0  5173.7     0.1       0
  5346.9   0.035       0  5427.9     0.1       0  5555.9    0.07       0
Bank Sta=5002.9,5009.2
Exp/Cntr=0.3,0.1

Type RM Length L Ch R = 1,5503,480,480,480
BEGIN DESCRIPTION:
Stream0096 11.0
END DESCRIPTION:
XS GIS Cut Line= 3
      1998425.01     13890425.00      1998825.00     13890325.00
      1999225.01     13890725.01
#Sta/Elev= 30
  4583.2 1474.35  4592.5 1472.35  4632.7 1459.49  4675.9 1452.72  4686.6 1450.11
  4747.1 1446.58  4786.2 1445.72  4830.1 1444.47  4892.4 1445.80  4966.6 1445.35
  5003.6 1440.98  5018.2 1439.28  5018.7 1438.78  5024.5 1439.28  5069.9 1444.61
  5142.0 1447.98  5199.6 1452.98  5269.6 1456.56  5290.3 1458.59  5309.9 1461.19
  5329.0 1467.88  5333.5 1471.39  5345.7 1475.11  5367.2 1478.47  5392.9 1479.36
  5426.8 1483.54  5483.8 1498.84  5507.2 1511.13  5519.9 1519.23  5561.2 1525.64
#Mann=7,-1,0
  4583.2   0.035       0  4786.2     0.1       0  5003.6   0.035       0
  5018.2    0.05       0  5024.5   0.035       0  5142.0    0.07       0
  5290.3     0.1       0
Bank Sta=5018.2,5024.5
Exp/Cntr=0.3,0.1

Type RM Length L Ch R = 1,5023,419,419,419
BEGIN DESCRIPTION:
Stream0096 10.0
END DESCRIPTION:
XS GIS Cut Line= 3
      1998375.00     13890475.00      1998725.00     13890775.00
      1999125.02     13890875.00
#Sta/Elev= 30
  4534.4 1478.30  4554.0 1477.30  4572.6 1474.59  4604.2 1467.54  4619.8 1462.47
  4655.6 1454.71  4671.4 1450.13  4690.1 1447.23  4824.2 1439.96  4900.5 1441.42
  4960.3 1440.06  4998.3 1433.41  4998.8 1432.91  5004.7 1433.41  5037.0 1439.55
  5063.9 1441.03  5119.1 1443.79  5207.5 1451.70  5230.4 1455.77  5246.6 1461.26
  5255.1 1464.94  5273.7 1476.01  5295.3 1482.61  5310.8 1489.55  5344.8 1496.34
  5354.1 1499.76  5363.3 1505.86  5376.6 1512.53  5385.0 1518.66  5407.7 1525.32
#Mann=6,-1,0
  4534.4   0.035       0  4998.3   0.035       0  5004.7   0.035       0
  5037.0    0.07       0  5063.9   0.035       0  5246.6     0.1       0
Bank Sta=4998.3,5004.7
Exp/Cntr=0.3,0.1