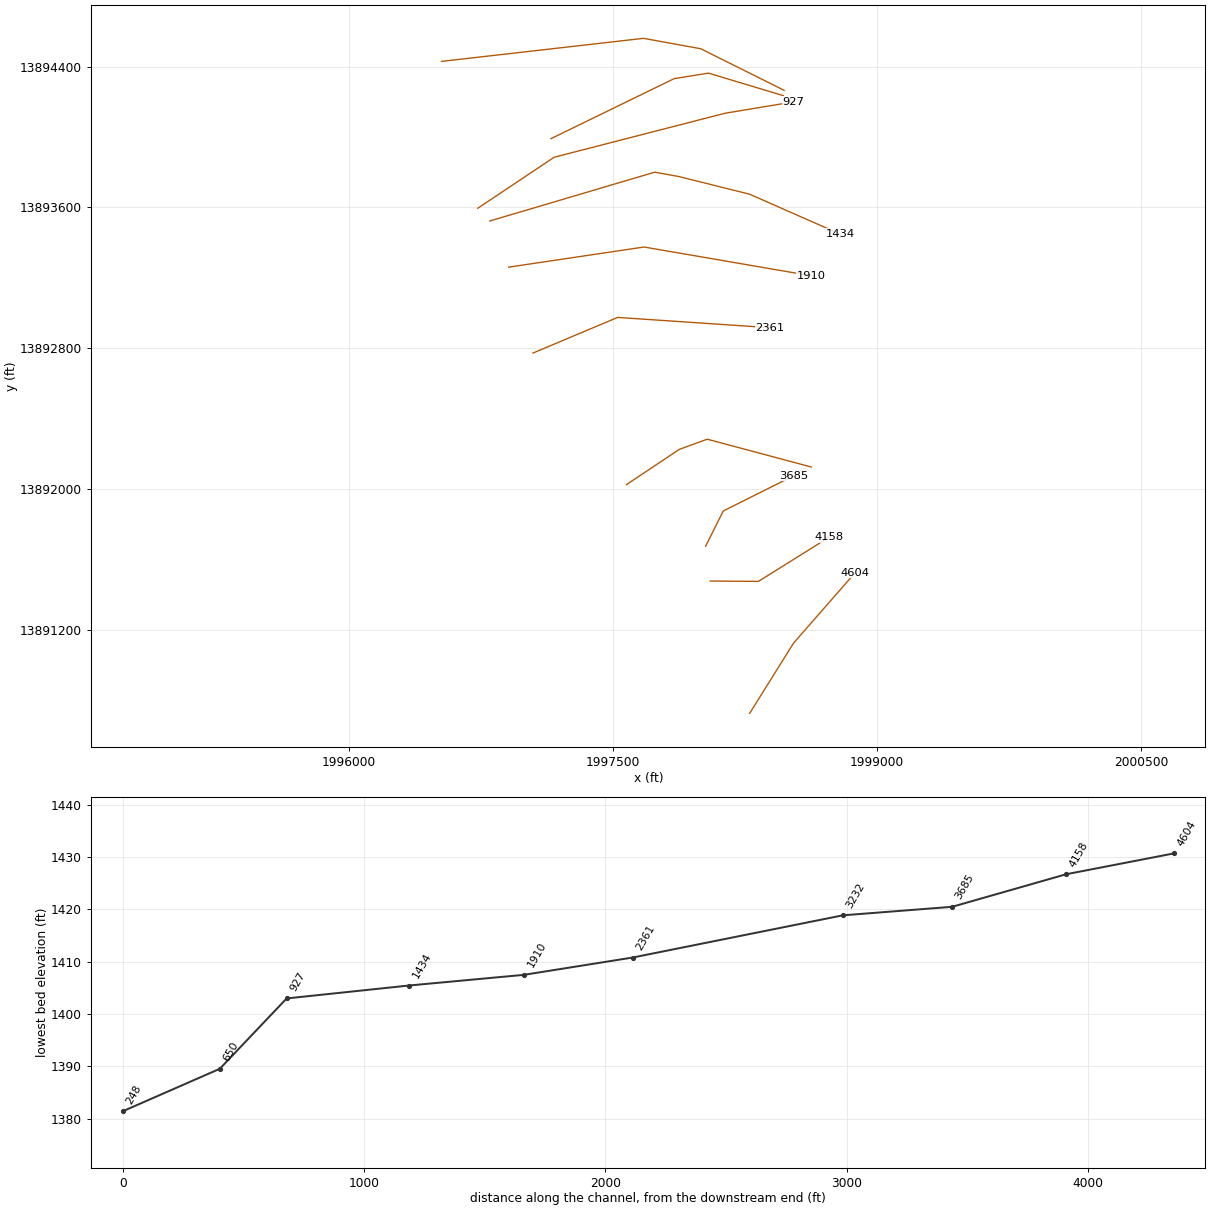
HEC-RAS study Stream0096.prj: Stream0096 Base Level Engineering

--- Stream0096.g01 (geometry) --- (continued)

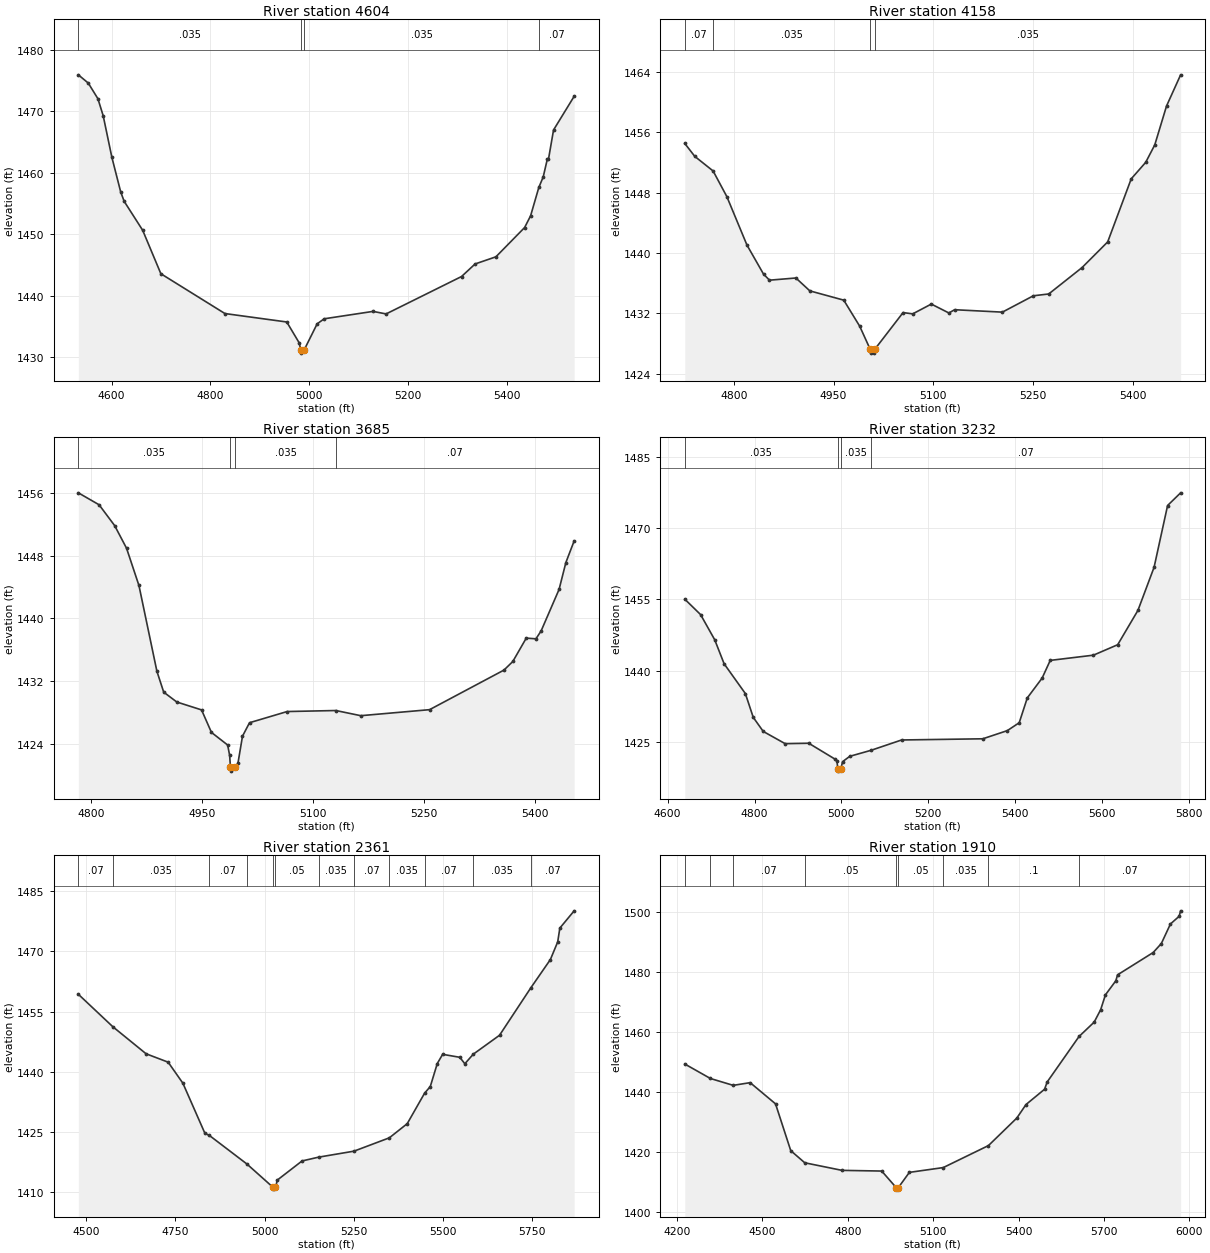
Type RM Length L Ch R = 1,4604,446,446,446
BEGIN DESCRIPTION:
Stream0096 9.0
END DESCRIPTION:
XS GIS Cut Line= 3
      1998274.98     13890724.97      1998525.00     13891125.00
      1998874.97     13891524.97
#Sta/Elev= 30
  4532.7 1475.91  4552.8 1474.57  4572.3 1472.03  4583.0 1469.26  4600.6 1462.49
  4618.4 1456.89  4625.4 1455.36  4662.9 1450.65  4699.7 1443.59  4829.3 1437.12
  4954.4 1435.75  4979.2 1432.41  4983.1 1431.19  4983.6 1430.69  4989.5 1431.19
  5015.9 1435.45  5030.2 1436.27  5128.9 1437.47  5155.4 1437.06  5308.1 1443.14
  5335.5 1445.18  5377.6 1446.34  5435.7 1451.10  5447.8 1453.01  5464.4 1457.61
  5473.3 1459.32  5481.8 1462.28  5483.9 1462.17  5494.2 1466.95  5535.9 1472.42
#Mann=4,-1,0
  4532.7   0.035       0  4983.1   0.035       0  4989.5   0.035       0
  5464.4    0.07       0
Bank Sta=4983.1,4989.5
Exp/Cntr=0.3,0.1

Type RM Length L Ch R = 1,4158,473,473,473
BEGIN DESCRIPTION:
Stream0096 8.0
END DESCRIPTION:
XS GIS Cut Line= 3
      1998050.90     13891476.90      1998325.00     13891475.00
      1998725.00     13891725.00
#Sta/Elev= 30
  4726.3 1454.53  4741.3 1452.82  4768.9 1450.88  4789.6 1447.47  4819.8 1441.05
  4844.7 1437.20  4853.7 1436.39  4893.4 1436.68  4914.4 1434.97  4965.4 1433.74
  4989.4 1430.28  5005.2 1427.21  5005.7 1426.71  5011.5 1426.71  5012.0 1427.21
  5054.6 1432.09  5069.1 1431.92  5097.1 1433.22  5123.5 1432.04  5132.2 1432.47
  5204.0 1432.15  5250.6 1434.32  5273.7 1434.56  5323.8 1438.06  5362.4 1441.47
  5397.8 1449.84  5419.6 1452.03  5433.2 1454.34  5450.9 1459.50  5472.1 1463.64
#Mann=4,-1,0
  4726.3    0.07       0  4768.9   0.035       0  5005.2   0.035       0
  5012.0   0.035       0
Bank Sta=5005.2,5012
Exp/Cntr=0.3,0.1

Type RM Length L Ch R = 1,3685,453,453,453
BEGIN DESCRIPTION:
Stream0096 7.0
END DESCRIPTION:
XS GIS Cut Line= 3
      1998025.00     13891674.99      1998125.00     13891875.00
      1998524.97     13892074.99
#Sta/Elev= 30
  4782.5 1456.07  4810.6 1454.54  4831.7 1451.87  4847.7 1448.99  4864.5 1444.22
  4888.8 1433.25  4898.0 1430.58  4915.7 1429.32  4949.2 1428.31  4962.6 1425.43
  4984.5 1423.82  4987.2 1422.50  4988.3 1420.98  4988.8 1420.48  4995.1 1420.98
  4998.4 1421.46  5004.6 1424.95  5014.1 1426.67  5065.0 1428.10  5130.9 1428.23
  5164.6 1427.57  5257.7 1428.34  5358.3 1433.40  5370.3 1434.50  5388.5 1437.49
  5401.6 1437.40  5408.6 1438.41  5432.9 1443.72  5442.1 1447.16  5453.3 1449.92
#Mann=4,-1,0
  4782.5   0.035       0  4988.3   0.035       0  4995.1   0.035       0
  5130.9    0.07       0
Bank Sta=4988.3,4995.1
Exp/Cntr=0.3,0.1

Type RM Length L Ch R = 1,3232,871,871,871
BEGIN DESCRIPTION:
Stream0096 6.0
END DESCRIPTION:
XS GIS Cut Line= 4
      1997575.03     13892025.02      1997875.00     13892225.00
      1998034.13     13892282.99      1998624.98     13892125.00
#Sta/Elev= 30
  4639.5 1455.06  4675.9 1451.81  4708.4 1446.51  4730.0 1441.46  4778.9 1435.19
  4797.1 1430.17  4820.1 1427.21  4870.6 1424.63  4924.9 1424.72  4986.0 1421.34
  4989.8 1421.01  4991.7 1419.35  4992.2 1418.85  4998.6 1419.35  5002.9 1420.85
  5019.3 1421.97  5068.5 1423.24  5138.6 1425.41  5325.6 1425.66  5382.0 1427.38
  5409.4 1429.04  5428.0 1434.27  5462.2 1438.45  5480.8 1442.17  5580.2 1443.27
  5636.1 1445.47  5682.7 1452.70  5719.9 1461.78  5751.0 1474.79  5781.0 1477.46
#Mann=4,-1,0
  4639.5   0.035       0  4991.7   0.035       0  4998.6   0.035       0
  5068.5    0.07       0
Bank Sta=4991.7,4998.6
Exp/Cntr=0.3,0.1

Type RM Length L Ch R = 1,2361,451,451,451
BEGIN DESCRIPTION:
Stream0096 5.0
END DESCRIPTION:
XS GIS Cut Line= 3
      1997043.63     13892772.47      1997525.00     13892975.00
      1998389.99     13892916.59
#Sta/Elev= 30
  4478.2 1459.34  4574.8 1451.25  4668.0 1444.51  4729.9 1442.41  4771.1 1437.18
  4832.9 1424.68  4844.9 1424.19  4950.4 1417.05  5023.1 1411.28  5023.6 1410.78
  5030.5 1411.28  5035.9 1413.05  5105.0 1417.80  5151.5 1418.75  5250.5 1420.24
  5349.5 1423.56  5399.7 1427.09  5448.5 1434.71  5464.3 1436.34  5483.9 1442.08
  5498.9 1444.37  5547.0 1443.63  5561.1 1442.02  5584.8 1444.41  5658.3 1449.12
  5745.5 1460.88  5800.8 1467.99  5821.3 1472.39  5827.3 1475.83  5867.4 1480.13
#Mann=12,-1,0
  4478.2    0.07       0  4574.8   0.035       0  4844.9    0.07       0
  4950.4    0.05       0  5023.1    0.05       0  5030.5    0.05       0
  5151.5   0.035       0  5250.5    0.07       0  5349.5   0.035       0
  5448.5    0.07       0  5584.8   0.035       0  5745.5    0.07       0
Bank Sta=5023.1,5030.5
Exp/Cntr=0.3,0.1

Type RM Length L Ch R = 1,1910,476,476,476
BEGIN DESCRIPTION:
Stream0096 4.0
END DESCRIPTION:
XS GIS Cut Line= 3
      1996906.09     13893260.73      1997675.00     13893375.00
      1998625.30     13893211.56
#Sta/Elev= 30
  4227.4 1449.21  4317.3 1444.38  4397.4 1442.09  4457.0 1442.99  4546.1 1435.92
  4599.6 1420.30  4648.8 1416.26  4779.6 1413.73  4919.1 1413.50  4970.0 1407.97
  4970.5 1407.47  4977.4 1407.97  5016.2 1413.06  5135.2 1414.66  5294.0 1422.00
  5393.7 1431.19  5425.9 1435.69  5491.1 1440.79  5500.3 1443.22  5612.2 1458.39
  5665.3 1463.18  5688.1 1467.32  5704.9 1472.29  5741.4 1476.97  5747.5 1478.96
  5872.6 1486.40  5901.2 1489.39  5933.2 1495.92  5963.6 1498.47  5969.0 1500.31
#Mann=9,-1,0
  4227.4    0.07       0  4317.3    0.05       0  4397.4    0.07       0
  4648.8    0.05       0  4970.0    0.05       0  4977.4    0.05       0
  5135.2   0.035       0  5294.0     0.1       0  5612.2    0.07       0
Bank Sta=4970,4977.4
Exp/Cntr=0.3,0.1

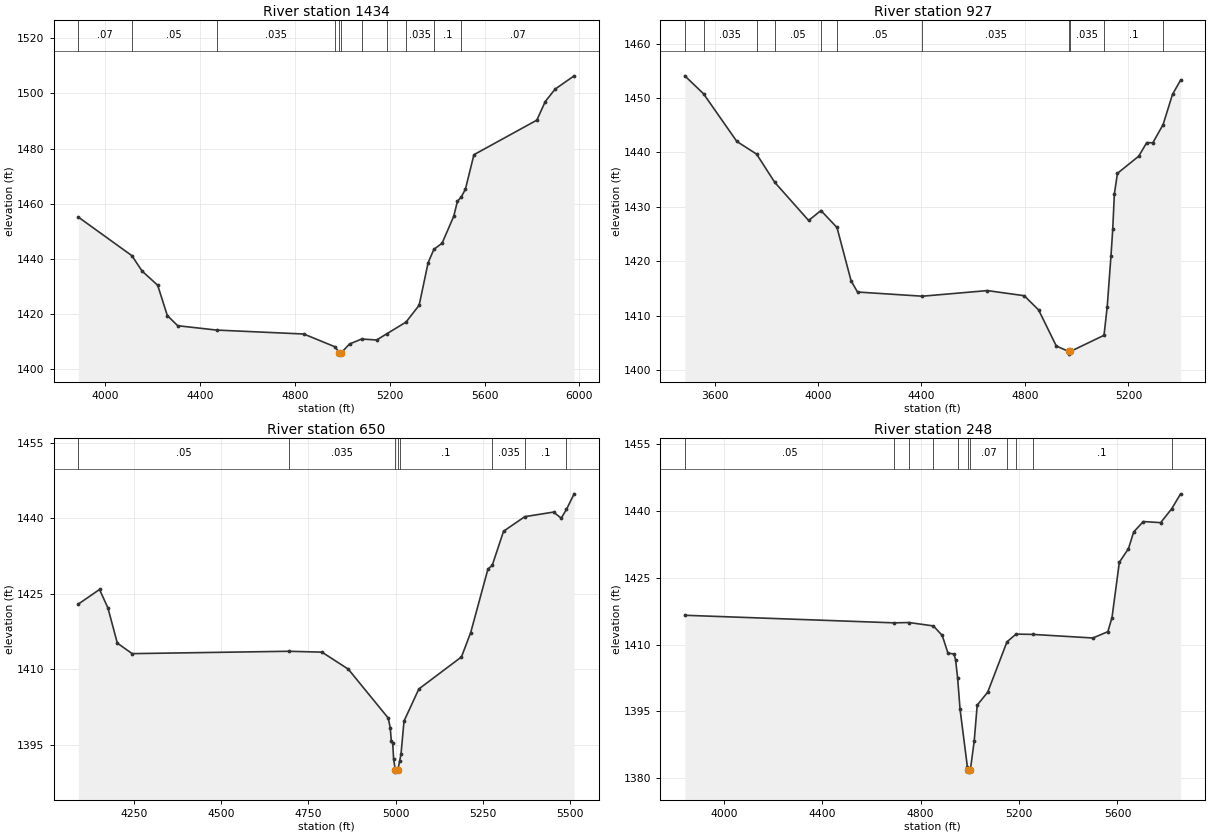
Type RM Length L Ch R = 1,1434,507,507,507
BEGIN DESCRIPTION:
Stream0096 3.0
END DESCRIPTION:
XS GIS Cut Line= 5
      1996798.27     13893522.89      1997735.78     13893800.33
      1997875.00     13893775.00      1998275.00     13893675.00
      1998788.01     13893448.98
#Sta/Elev= 30
  3885.5 1455.14  4111.3 1441.16  4154.6 1435.56  4220.3 1430.42  4260.9 1419.44
  4304.8 1415.74  4468.5 1414.16  4836.7 1412.73  4967.8 1408.11  4987.2 1405.93
  4987.7 1405.43  4994.7 1405.93  5029.8 1409.10  5080.9 1410.91  5144.2 1410.56
  5186.8 1412.80  5268.1 1417.05  5323.6 1423.17  5361.3 1438.56  5385.6 1443.43
  5420.3 1445.67  5469.5 1455.44  5484.9 1460.82  5501.9 1462.55  5518.6 1465.22
  5554.7 1477.78  5820.1 1490.31  5855.7 1497.06  5897.5 1501.59  5977.6 1506.39
#Mann=11,-1,0
  3885.5    0.07       0  4111.3    0.05       0  4468.5   0.035       0
  4967.8    0.07       0  4987.2    0.05       0  4994.7    0.07       0
  5080.9   0.035       0  5186.8    0.07       0  5268.1   0.035       0
  5385.6     0.1       0  5501.9    0.07       0
Bank Sta=4987.2,4994.7
Exp/Cntr=0.3,0.1

Type RM Length L Ch R = 1,927,277,277,277
BEGIN DESCRIPTION:
Stream0096 2.0
END DESCRIPTION:
XS GIS Cut Line= 4
      1996730.29     13893595.37      1997164.16     13893885.13
      1998134.71     13894135.07      1998521.88     13894199.29
#Sta/Elev= 30
  3485.2 1454.08  3557.5 1450.79  3686.3 1442.03  3762.7 1439.70  3833.0 1434.51
  3963.8 1427.51  4011.4 1429.34  4073.4 1426.22  4127.9 1416.43  4152.7 1414.37
  4403.4 1413.60  4654.6 1414.63  4797.2 1413.69  4852.8 1411.07  4921.0 1404.46
  4968.3 1403.46  4968.8 1402.96  4975.9 1403.46  5105.5 1406.42  5117.9 1411.68
  5132.4 1421.00  5139.2 1425.88  5145.5 1432.38  5157.4 1436.17  5239.5 1439.31
  5270.7 1441.81  5294.2 1441.78  5333.9 1445.13  5370.3 1450.68  5401.6 1453.30
#Mann=11,-1,0
  3485.2    0.07       0  3557.5   0.035       0  3762.7    0.07       0
  3833.0    0.05       0  4011.4   0.035       0  4073.4    0.05       0
  4403.4   0.035       0  4968.3   0.035       0  4975.9   0.035       0
  5105.5     0.1       0  5333.9    0.07       0
Bank Sta=4968.3,4975.9
Exp/Cntr=0.3,0.1

Type RM Length L Ch R = 1,650,402,402,402
BEGIN DESCRIPTION:
Stream0096 1.1
END DESCRIPTION:
XS GIS Cut Line= 4
      1997145.72     13893990.58      1997846.26     13894331.92
      1998041.16     13894363.17      1998466.55     13894235.11
#Sta/Elev= 30
  4090.6 1422.94  4151.3 1425.84  4175.4 1422.18  4202.3 1415.18  4244.8 1413.08
  4693.0 1413.55  4788.7 1413.38  4864.2 1410.00  4978.5 1400.28  4984.4 1398.37
  4987.4 1395.80  4991.6 1395.23  4994.2 1392.05  4998.8 1390.01  4999.3 1389.51
  5006.4 1390.01  5011.4 1391.72  5015.2 1393.03  5023.9 1399.66  5066.4 1406.05
  5188.6 1412.43  5215.0 1417.27  5264.5 1429.92  5276.6 1430.62  5309.2 1437.43
  5370.1 1440.33  5452.4 1441.24  5474.4 1440.03  5489.5 1441.78  5511.5 1444.87
#Mann=8,-1,0
  4090.6    0.05       0  4693.0   0.035       0  4998.8   0.035       0
  5006.4   0.035       0  5011.4     0.1       0  5276.6   0.035       0
  5370.1     0.1       0  5489.5    0.07       0
Bank Sta=4998.8,5006.4
Exp/Cntr=0.3,0.1

Type RM Length L Ch R = 1,248,0,0,0
BEGIN DESCRIPTION:
Stream0096 1.0
END DESCRIPTION:
XS GIS Cut Line= 4
      1996523.80     13894429.76      1997671.82     13894560.82
      1997997.17     13894501.66      1998470.68     13894265.50
#Sta/Elev= 30
  3841.4 1416.60  4691.8 1414.90  4752.7 1414.97  4851.6 1414.21  4887.7 1412.08
  4911.1 1408.09  4935.5 1407.91  4942.0 1406.60  4950.4 1402.49  4960.2 1395.50
  4990.3 1382.43  4994.2 1381.89  4994.7 1381.39  5002.1 1381.89  5017.7 1388.37
  5029.9 1396.43  5072.6 1399.34  5151.0 1410.64  5187.6 1412.37  5254.7 1412.31
  5500.2 1411.50  5560.9 1412.92  5577.7 1416.06  5607.7 1428.51  5644.7 1431.55
  5666.0 1435.31  5705.1 1437.64  5775.5 1437.39  5820.4 1440.51  5856.7 1443.86
#Mann=11,-1,0
  3841.4    0.05       0  4691.8     0.1       0  4752.7    0.07       0
  4851.6     0.1       0  4950.4    0.07       0  4994.2    0.05       0
  5002.1    0.07       0  5151.0     0.1       0  5187.6   0.035       0
  5254.7     0.1       0  5820.4    0.07       0
Bank Sta=4994.2,5002.1
Exp/Cntr=0.3,0.1

Chan Stop Cuts=-1