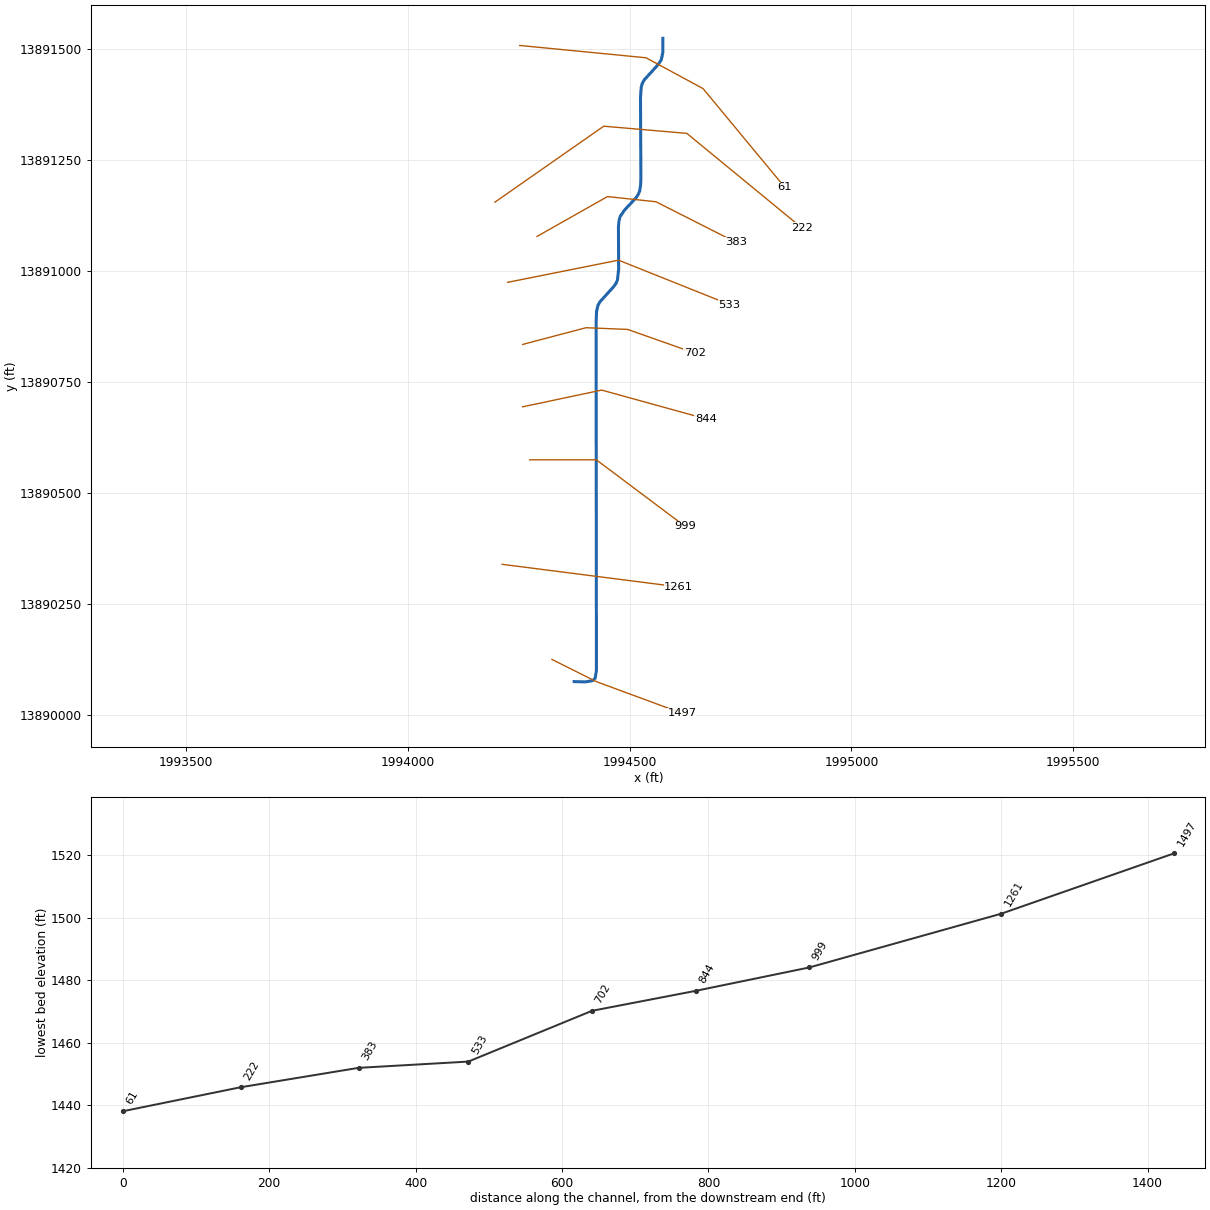
--- Stream0115.prj (project) ---

Proj Title=Stream0115 Base Level Engineering
Current Plan=p01
Default Exp/Contr=0.3,0.1
English Units
Geom File=g01
Flow File=f01
Plan File=p01
BEGIN DESCRIPTION:
Stream0115
END DESCRIPTION:

--- Stream0115.p01 (plan) ---

Plan Title=Multiple Run
Short Identifier=Multiple
Geom File=g01
Flow File=f01
Subcritical Flow
K Sum by GR= 0
Std Step Tol= 0.01
Critical Tol= 0.01
Num of Std Step Trials= 20
Max Error Tol= 0.3
Flow Tol Ratio= 0.001
Split Flow NTrial= 30
Split Flow Tol= 0.02
Split Flow Ratio= 0.02
Log Output Level= 0
Friction Slope Method= 1
Unsteady Friction Slope Method= 2
Unsteady Bridges Friction Slope Method= 1
Parabolic Critical Depth
Global Vel Dist=  1 , 1 , 1
Global Log Level= 0
CheckData=True
Encroach Param= -1, 0, 0, 0
BEGIN DESCRIPTION:
Multiple Run
END DESCRIPTION:

--- Stream0115.f01 (steady flow) ---

Flow Title=Multiple
Number of Profiles=7
Profile Names=10-year,25-year,50-year,1pct_min,100-year,1pct_plu,500-year
River Rch & RM= Stream0115,Reach-1,1497
     168     253     325     205     408     814     631
Boundary for River Rch & Prof#=Stream0115,Reach-1,1
Up Type=0
Dn Type=3
Dn Slope=0.005
Boundary for River Rch & Prof#=Stream0115,Reach-1,2
Up Type=0
Dn Type=3
Dn Slope=0.005
Boundary for River Rch & Prof#=Stream0115,Reach-1,3
Up Type=0
Dn Type=3
Dn Slope=0.005
Boundary for River Rch & Prof#=Stream0115,Reach-1,4
Up Type=0
Dn Type=3
Dn Slope=0.005
Boundary for River Rch & Prof#=Stream0115,Reach-1,5
Up Type=0
Dn Type=3
Dn Slope=0.005
Boundary for River Rch & Prof#=Stream0115,Reach-1,6
Up Type=0
Dn Type=3
Dn Slope=0.005
Boundary for River Rch & Prof#=Stream0115,Reach-1,7
Up Type=0
Dn Type=3
Dn Slope=0.005

--- Stream0115.g01 (geometry) ---

Geom Title=Existing Conditions

River Reach=Stream0115,Reach-1
Reach XY= 30
      1994375.00     13890075.00      1994400.78     13890074.42
      1994417.18     13890077.37      1994422.30     13890082.70
      1994425.19     13890099.81      1994424.55     13890885.19
      1994425.52     13890909.78      1994428.78     13890923.43
      1994433.14     13890931.06      1994464.14     13890965.36
      1994469.25     13890972.67      1994472.73     13890980.94
      1994475.32     13891004.87      1994474.82     13891100.07
      1994476.23     13891114.49      1994478.79     13891123.43
      1994488.80     13891138.14      1994514.15     13891165.35
      1994519.25     13891172.67      1994522.74     13891180.94
      1994524.93     13891195.03      1994525.43     13891209.82
      1994524.56     13891390.18      1994526.12     13891414.54
      1994528.60     13891423.51      1994532.89     13891431.16
      1994563.94     13891465.44      1994571.35     13891476.51
      1994574.88     13891493.20      1994575.00     13891525.00

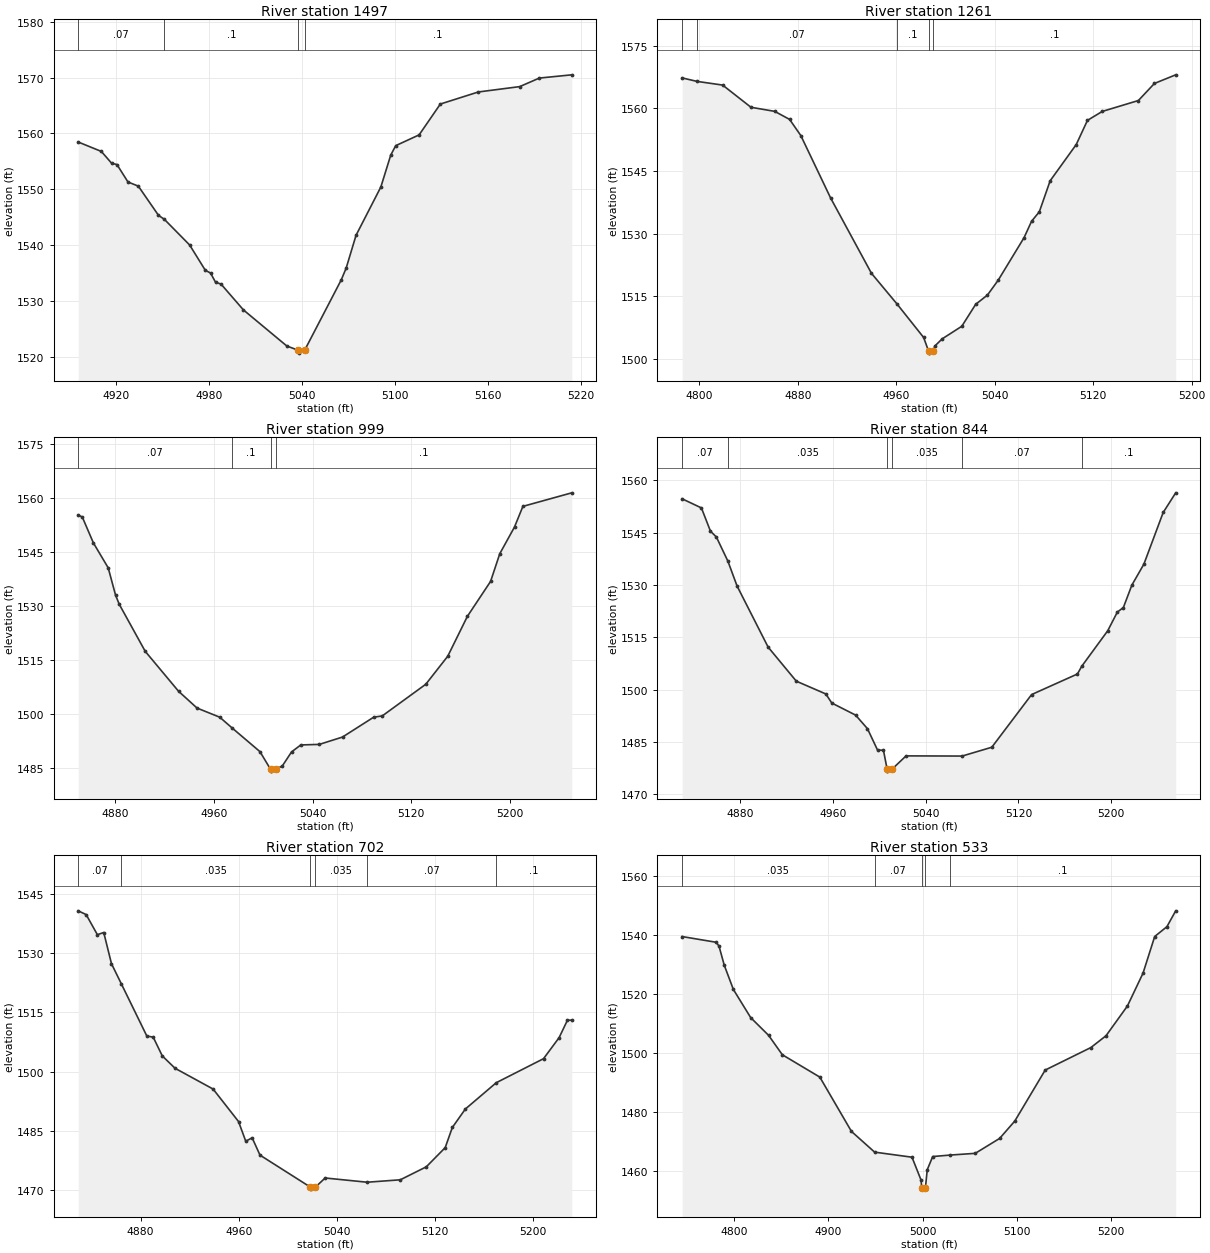
Type RM Length L Ch R = 1,1497,236,236,236
BEGIN DESCRIPTION:
Stream0115 3.0
END DESCRIPTION:
XS GIS Cut Line= 3
      1994324.99     13890125.01      1994425.00     13890075.00
      1994618.89     13890003.42
#Sta/Elev= 30
  4895.5 1558.45  4910.4 1556.77  4917.1 1554.64  4920.5 1554.42  4927.6 1551.30
  4934.3 1550.55  4947.3 1545.33  4951.1 1544.61  4967.4 1540.02  4977.5 1535.50
  4980.9 1534.99  4984.2 1533.31  4987.6 1533.04  5002.1 1528.40  5030.1 1521.94
  5037.6 1521.16  5037.9 1520.66  5041.6 1521.16  5065.2 1533.75  5068.4 1535.86
  5074.8 1541.76  5090.8 1550.40  5097.2 1556.12  5100.4 1557.80  5115.5 1559.73
  5129.2 1565.25  5153.7 1567.41  5180.4 1568.37  5193.1 1569.90  5214.0 1570.48
#Mann=4,-1,0
  4895.5    0.07       0  4951.1     0.1       0  5037.6    0.05       0
  5041.6     0.1       0
Bank Sta=5037.6,5041.6
Exp/Cntr=0.3,0.1

Type RM Length L Ch R = 1,1261,262,262,262
BEGIN DESCRIPTION:
Stream0115 4.0
END DESCRIPTION:
XS GIS Cut Line= 2
      1994212.74     13890339.41      1994610.50     13890288.54
#Sta/Elev= 30
  4786.0 1567.32  4798.0 1566.49  4818.9 1565.60  4841.9 1560.28  4861.2 1559.30
  4873.3 1557.37  4882.4 1553.50  4906.6 1538.54  4939.8 1520.47  4960.6 1513.10
  4982.2 1505.08  4986.2 1501.83  4986.5 1501.33  4990.2 1501.83  4991.2 1503.01
  4997.3 1504.76  5013.2 1507.77  5024.5 1513.04  5034.0 1515.24  5042.7 1518.78
  5063.8 1529.02  5069.9 1532.95  5076.2 1535.22  5085.0 1542.66  5106.2 1551.35
  5115.3 1557.14  5127.3 1559.28  5156.7 1561.90  5169.7 1565.99  5187.0 1568.06
#Mann=5,-1,0
  4786.0   0.035       0  4798.0    0.07       0  4960.6     0.1       0
  4986.2    0.05       0  4990.2     0.1       0
Bank Sta=4986.2,4990.2
Exp/Cntr=0.3,0.1

Type RM Length L Ch R = 1,999,155,155,155
BEGIN DESCRIPTION:
Stream0115 2.0
END DESCRIPTION:
XS GIS Cut Line= 3
      1994275.00     13890575.00      1994425.00     13890575.00
      1994625.00     13890425.00
#Sta/Elev= 30
  4850.0 1555.21  4853.3 1554.67  4862.3 1547.47  4874.3 1540.56  4880.3 1532.93
  4883.3 1530.41  4904.3 1517.38  4931.3 1506.30  4946.3 1501.63  4964.7 1499.09
  4974.3 1496.23  4997.3 1489.53  5005.9 1484.62  5006.2 1484.12  5009.9 1484.62
  5015.4 1485.54  5022.9 1489.45  5030.4 1491.39  5045.4 1491.54  5064.2 1493.58
  5089.5 1499.10  5096.4 1499.44  5131.7 1508.24  5149.5 1516.02  5165.4 1527.08
  5184.2 1536.78  5191.7 1544.50  5203.6 1551.89  5210.4 1557.62  5250.0 1561.38
#Mann=4,-1,0
  4850.0    0.07       0  4974.3     0.1       0  5005.9    0.05       0
  5009.9     0.1       0
Bank Sta=5005.9,5009.9
Exp/Cntr=0.3,0.1

Type RM Length L Ch R = 1,844,142,142,142
BEGIN DESCRIPTION:
Stream0115 A
END DESCRIPTION:
XS GIS Cut Line= 3
      1994258.77     13890694.38      1994437.13     13890732.13
      1994671.44     13890667.41
#Sta/Elev= 30
  4830.1 1554.70  4846.7 1552.09  4854.5 1545.42  4859.6 1543.75  4869.5 1536.84
  4877.4 1529.72  4904.2 1512.18  4928.5 1502.42  4953.9 1498.76  4959.1 1496.15
  4979.6 1492.69  4989.8 1488.81  4998.5 1482.67  5003.6 1482.61  5006.8 1477.13
  5007.0 1476.63  5010.8 1477.13  5023.1 1481.00  5071.4 1480.95  5097.0 1483.48
  5131.3 1498.58  5170.8 1504.48  5174.5 1506.69  5196.9 1516.87  5205.2 1522.23
  5210.4 1523.54  5217.7 1529.95  5228.1 1535.99  5244.7 1550.78  5255.5 1556.42
#Mann=6,-1,0
  4830.1    0.07       0  4869.5   0.035       0  5006.8   0.035       0
  5010.8   0.035       0  5071.4    0.07       0  5174.5     0.1       0
Bank Sta=5006.8,5010.8
Exp/Cntr=0.3,0.1

Type RM Length L Ch R = 1,702,169,169,169
BEGIN DESCRIPTION:
Stream0115 B
END DESCRIPTION:
XS GIS Cut Line= 4
      1994258.75     13890835.00      1994401.98     13890872.76
      1994495.73     13890868.85      1994646.72     13890815.48
#Sta/Elev= 30
  4829.2 1540.69  4835.7 1539.73  4844.8 1534.65  4850.0 1535.20  4856.3 1527.30
  4864.4 1522.16  4885.1 1508.99  4890.3 1508.70  4897.7 1503.95  4908.1 1500.82
  4939.1 1495.56  4959.8 1487.34  4965.7 1482.35  4970.9 1483.22  4977.3 1478.83
  5018.4 1470.72  5018.6 1470.22  5022.4 1470.72  5030.4 1473.04  5064.6 1471.97
  5091.6 1472.58  5112.8 1475.87  5128.2 1480.73  5134.0 1485.83  5144.6 1490.50
  5169.8 1497.17  5208.3 1503.25  5221.0 1508.58  5227.8 1513.00  5231.3 1513.00
#Mann=6,-1,0
  4829.2    0.07       0  4864.4   0.035       0  5018.4   0.035       0
  5022.4   0.035       0  5064.6    0.07       0  5169.8     0.1       0
Bank Sta=5018.4,5022.4
Exp/Cntr=0.3,0.1

Type RM Length L Ch R = 1,533,150,150,150
BEGIN DESCRIPTION:
Stream0115 1.0
END DESCRIPTION:
XS GIS Cut Line= 3
      1994225.01     13890975.00      1994475.00     13891025.00
      1994725.00     13890925.00
#Sta/Elev= 30
  4744.7 1539.62  4780.7 1537.69  4783.8 1536.42  4789.4 1529.91  4799.1 1521.67
  4817.5 1512.12  4836.5 1506.12  4851.1 1499.53  4890.9 1491.95  4924.5 1473.53
  4949.1 1466.50  4988.8 1464.78  4998.5 1456.97  4999.1 1454.45  4999.3 1453.95
  5003.1 1454.45  5005.0 1460.53  5010.8 1465.00  5029.2 1465.50  5056.0 1466.09
  5081.9 1471.15  5098.0 1477.04  5130.3 1494.34  5178.8 1501.97  5194.9 1505.98
  5217.6 1516.06  5234.2 1527.21  5246.6 1539.64  5259.6 1542.98  5268.9 1548.35
#Mann=5,-1,0
  4744.7   0.035       0  4949.1    0.07       0  4999.1    0.05       0
  5003.1    0.07       0  5029.2     0.1       0
Bank Sta=4999.1,5003.1
Exp/Cntr=0.3,0.1

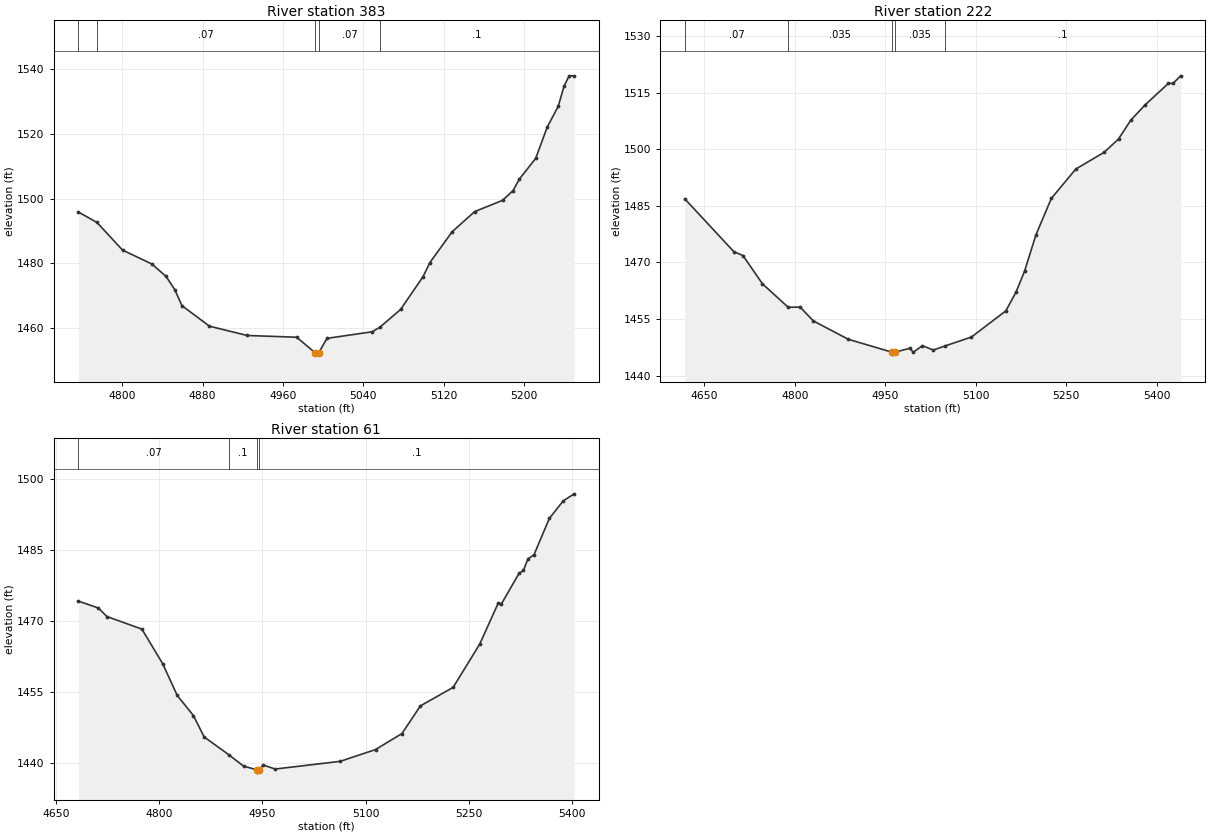
Type RM Length L Ch R = 1,383,161,161,161
BEGIN DESCRIPTION:
Stream0115 C
END DESCRIPTION:
XS GIS Cut Line= 4
      1994291.34     13891078.51      1994450.15     13891168.33
      1994559.53     13891156.61      1994739.18     13891065.48
#Sta/Elev= 30
  4756.2 1495.84  4774.8 1492.60  4800.2 1484.08  4829.3 1479.79  4843.5 1475.98
  4852.3 1471.86  4859.4 1466.92  4886.8 1460.57  4924.4 1457.70  4973.7 1457.16
  4991.8 1452.44  4992.1 1451.94  4995.8 1452.44  5003.9 1456.81  5048.7 1458.83
  5056.6 1460.25  5077.2 1465.73  5099.6 1475.87  5106.4 1480.23  5128.6 1489.74
  5150.9 1495.94  5178.8 1499.44  5189.3 1502.47  5195.4 1505.94  5211.8 1512.41
  5223.3 1522.07  5234.2 1528.45  5240.0 1534.67  5245.1 1537.89  5250.1 1537.89
#Mann=5,-1,0
  4756.2   0.035       0  4774.8    0.07       0  4991.8    0.05       0
  4995.8    0.07       0  5056.6     0.1       0
Bank Sta=4991.8,4995.8
Exp/Cntr=0.3,0.1

Type RM Length L Ch R = 1,222,161,161,161
BEGIN DESCRIPTION:
Stream0115 0.0
END DESCRIPTION:
XS GIS Cut Line= 4
      1994196.48     13891155.78      1994441.67     13891326.95
      1994629.00     13891310.76      1994888.06     13891097.96
#Sta/Elev= 30
  4617.4 1486.85  4698.8 1472.86  4713.9 1471.84  4746.2 1464.35  4788.9 1458.14
  4808.7 1458.19  4830.6 1454.53  4888.4 1449.67  4961.3 1446.23  4961.5 1445.73
  4965.3 1446.23  4990.4 1447.27  4996.4 1446.24  5011.4 1447.96  5029.5 1446.81
  5048.9 1447.89  5092.7 1450.25  5149.8 1457.18  5166.6 1462.11  5180.8 1467.66
  5199.7 1477.29  5225.2 1486.95  5265.8 1494.74  5313.1 1499.21  5336.7 1502.71
  5357.2 1507.72  5380.5 1511.70  5419.3 1517.42  5427.1 1517.44  5439.7 1519.44
#Mann=5,-1,0
  4617.4    0.07       0  4788.9   0.035       0  4961.3   0.035       0
  4965.3   0.035       0  5048.9     0.1       0
Bank Sta=4961.3,4965.3
Exp/Cntr=0.3,0.1

Type RM Length L Ch R = 1,61,0,0,0
BEGIN DESCRIPTION:
Stream0115 0.1
END DESCRIPTION:
XS GIS Cut Line= 4
      1994252.33     13891508.96      1994537.06     13891481.18
      1994665.53     13891411.74      1994849.53     13891189.55
#Sta/Elev= 30
  4682.6 1474.13  4711.7 1472.68  4724.2 1470.87  4775.0 1468.22  4805.2 1460.92
  4826.3 1454.23  4849.8 1449.99  4865.5 1445.46  4901.0 1441.74  4922.7 1439.31
  4941.8 1438.54  4942.1 1438.04  4945.8 1438.54  4951.3 1439.54  4968.7 1438.69
  5063.3 1440.32  5114.5 1442.80  5152.9 1446.18  5179.8 1452.02  5227.3 1455.93
  5265.9 1465.04  5293.1 1473.79  5297.4 1473.51  5323.0 1479.97  5329.4 1480.60
  5336.0 1483.01  5344.9 1483.94  5367.1 1491.57  5387.2 1495.27  5403.2 1496.77
#Mann=4,-1,0
  4682.6    0.07       0  4901.0     0.1       0  4941.8    0.05       0
  4945.8     0.1       0
Bank Sta=4941.8,4945.8
Exp/Cntr=0.3,0.1

Chan Stop Cuts=-1