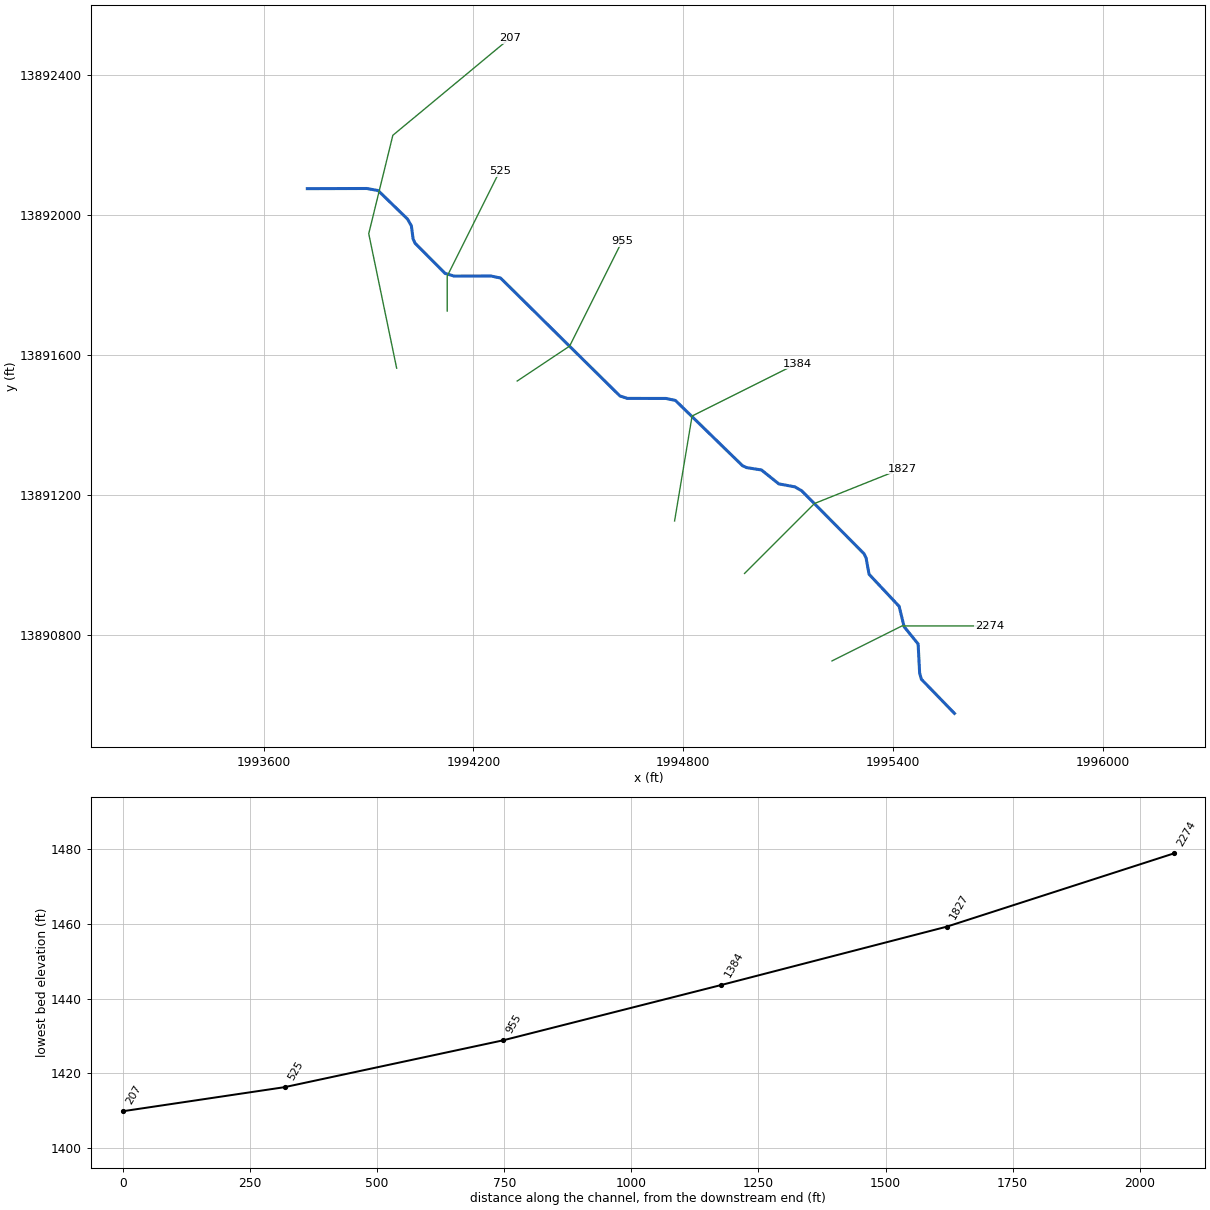
--- Stream0129.prj (project) ---

Proj Title=Stream0129 Base Level Engineering
Current Plan=p01
Default Exp/Contr=0.3,0.1
English Units
Geom File=g01
Flow File=f01
Plan File=p01
Y Axis Title=Elevation
X Axis Title(PF)=Main Channel Distance
X Axis Title(XS)=Station
BEGIN DESCRIPTION:
Stream0129
END DESCRIPTION:
DSS Export Rating Curves= 0
DSS Export Rating Curve Sorted= 0
DSS Export Volume Flow Curves= 0
DXF OffsetX= 0
DXF OffsetY= 0
DXF ScaleX= 1
DXF ScaleY= 10

--- Stream0129.p01 (plan) ---

Plan Title=Multiple Run
Short Identifier=Multiple
Geom File=g01
Flow File=f01
Subcritical Flow
K Sum by GR= 0
Std Step Tol= 0.01
Critical Tol= 0.01
Num of Std Step Trials= 20
Max Error Tol= 0.3
Flow Tol Ratio= 0.001
Split Flow NTrial= 30
Split Flow Tol= 0.02
Split Flow Ratio= 0.02
Log Output Level= 0
Friction Slope Method= 1
Unsteady Friction Slope Method= 2
Unsteady Bridges Friction Slope Method= 1
Parabolic Critical Depth
Global Vel Dist=  1 , 1 , 1
Global Log Level= 0
CheckData=True
Encroach Param= -1, 0, 0, 0
BEGIN DESCRIPTION:
Multiple Run
END DESCRIPTION:

--- Stream0129.f01 (steady flow) ---

Flow Title=Multiple
Number of Profiles=7
Profile Names=10-year,25-year,50-year,1pct_min,100-year,1pct_plu,500-year
River Rch & RM= Stream0129,Reach-1,2274
     236     365     477     305     609    1215     974
River Rch & RM= Stream0129,Reach-1,955
     396     636     854     559    1116    2226    1877
Boundary for River Rch & Prof#=Stream0129,Reach-1,1
Up Type=0
Dn Type=3
Dn Slope=0.005
Boundary for River Rch & Prof#=Stream0129,Reach-1,2
Up Type=0
Dn Type=3
Dn Slope=0.005
Boundary for River Rch & Prof#=Stream0129,Reach-1,3
Up Type=0
Dn Type=3
Dn Slope=0.005
Boundary for River Rch & Prof#=Stream0129,Reach-1,4
Up Type=0
Dn Type=3
Dn Slope=0.005
Boundary for River Rch & Prof#=Stream0129,Reach-1,5
Up Type=0
Dn Type=3
Dn Slope=0.005
Boundary for River Rch & Prof#=Stream0129,Reach-1,6
Up Type=0
Dn Type=3
Dn Slope=0.005
Boundary for River Rch & Prof#=Stream0129,Reach-1,7
Up Type=0
Dn Type=3
Dn Slope=0.005

--- Stream0129.g01 (geometry) ---

Geom Title=Existing Conditions
Program Version=4.10

River Reach=Stream0129      ,Reach-1
Reach XY= 30
        1995575.       13890575.      1995480.46     13890672.55
      1995475.51     13890690.21      1995471.17     13890773.42
      1995431.14     13890822.83      1995416.84     13890881.05
      1995330.87     13890972.72      1995322.47     13891018.95
      1995316.84     13891031.05      1995138.21     13891211.38
      1995118.96      13891222.5      1995072.81      13891231.1
      1995023.26     13891270.81      1994981.04      13891277.5
      1994968.94     13891283.14      1994777.45     13891469.54
      1994750.12     13891475.28      1994640.16     13891475.38
      1994618.65     13891482.44      1994277.45     13891819.53
      1994250.11     13891825.27      1994144.99     13891824.98
      1994118.79     13891832.81      1994033.15     13891918.93
      1994027.53     13891931.04      1994022.47     13891968.96
      1994011.38     13891988.24      1993927.47     13892069.55
      1993895.19     13892075.45        1993725.       13892075.

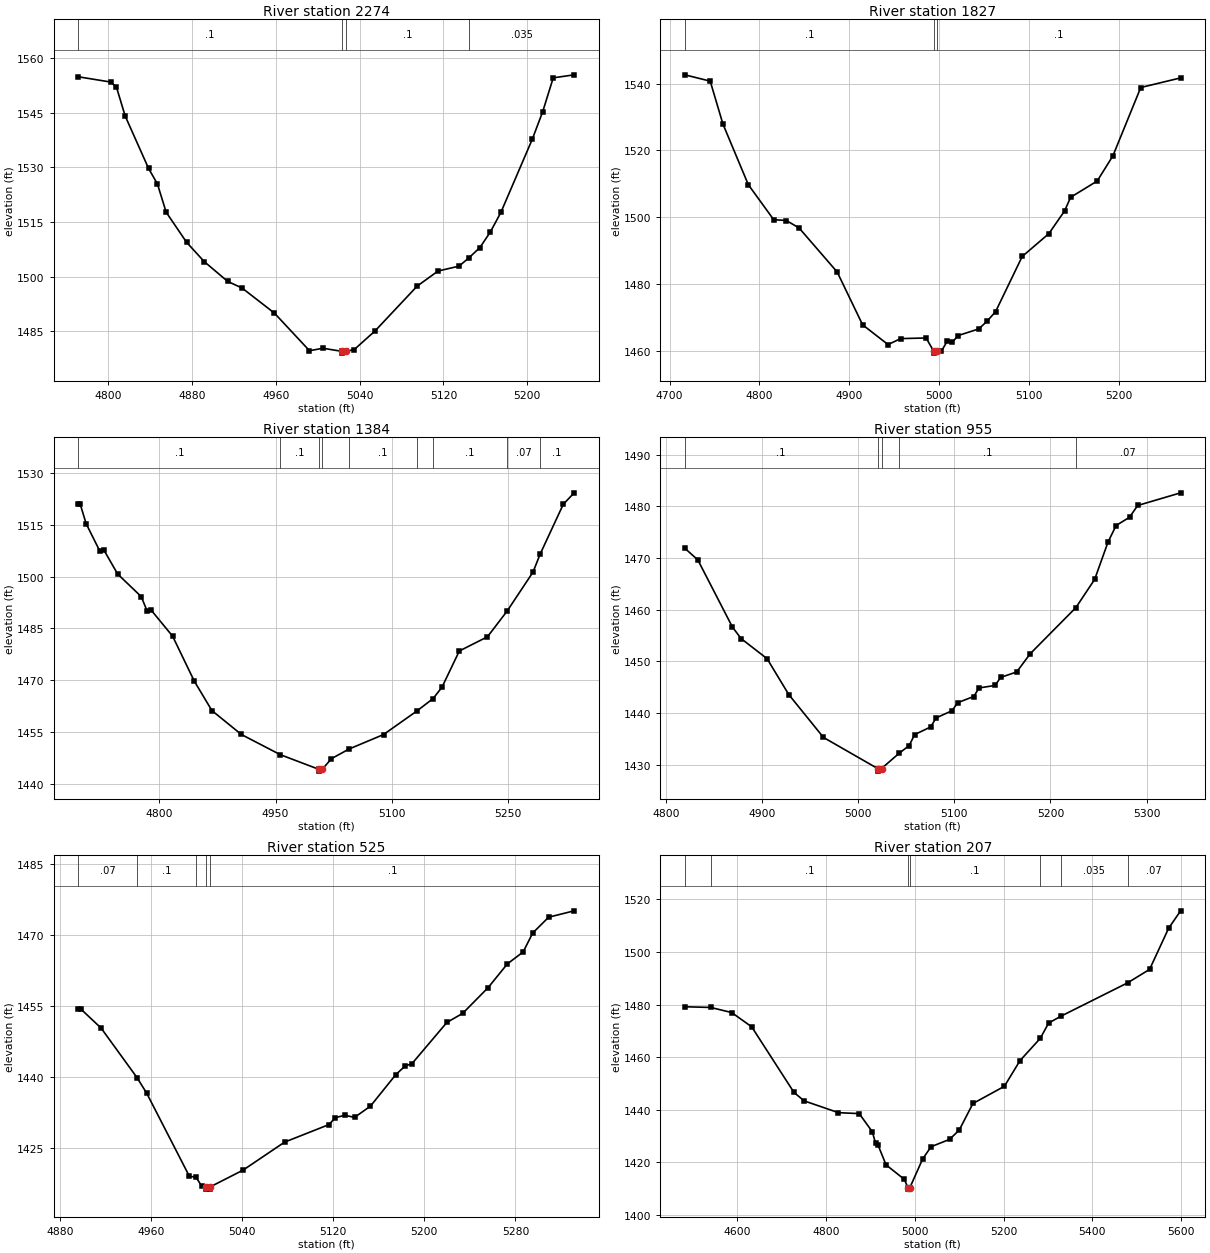
Type RM Length L Ch R = 1 ,2274    ,447,447,447
BEGIN DESCRIPTION:
Stream0129 5.0
END DESCRIPTION:
XS GIS Cut Line= 3
      1995224.98     13890724.99        1995425.       13890825.
      1995674.97       13890825.
#Sta/Elev= 30
  4771.3 1554.93  4802.1 1553.49  4807.7 1552.11    4816 1544.18  4838.4 1529.72
  4846.8  1525.5  4855.2 1517.69  4874.7 1509.43  4891.5 1504.13  4913.9 1498.68
  4927.8 1496.83  4958.6 1489.95  4992.1 1479.61  5004.9 1480.29  5022.9 1479.45
  5023.2 1478.95  5026.9 1479.45  5034.9 1479.94  5054.9 1485.11  5094.9 1497.36
  5114.9 1501.53  5134.9 1502.86  5144.6  1505.2  5154.9 1507.99  5164.9 1512.28
  5174.9 1517.64  5204.9 1537.76  5214.9 1545.38  5224.9 1554.64  5244.9 1555.47
#Mann= 4 ,-1 , 0
  4771.3      .1       0  5022.9     .05       0  5026.9      .1       0
  5144.6    .035       0
Bank Sta=5022.9,5026.9
XS Rating Curve= 0 ,0
Exp/Cntr=0.3,0.1

Type RM Length L Ch R = 1 ,1827    ,443,443,443
BEGIN DESCRIPTION:
Stream0129 4.0
END DESCRIPTION:
XS GIS Cut Line= 3
        1994975.       13890975.        1995175.       13891175.
      1995424.99       13891275.
#Sta/Elev= 30
  4716.9 1542.66  4745.2 1540.77  4759.3 1527.96  4787.6 1509.75  4815.9 1499.25
    4830 1499.01  4844.2 1496.76  4886.6 1483.57  4914.9 1467.75  4943.2 1461.84
  4957.3 1463.62  4985.6 1463.81  4994.2 1459.77  4994.5 1459.27  4998.2 1459.77
  5002.4 1459.77  5009.2 1462.87  5014.6 1462.49  5021.3 1464.54  5044.2 1466.52
  5053.6 1468.86    5063 1471.72  5092.6 1488.23  5122.3 1495.08  5139.8 1501.88
  5146.5 1505.96  5176.1 1510.84  5193.6 1518.39  5224.6 1538.86    5269 1541.74
#Mann= 3 ,-1 , 0
  4716.9      .1       0  4994.2     .05       0  4998.2      .1       0
Bank Sta=4994.2,4998.2
XS Rating Curve= 0 ,0
Exp/Cntr=0.3,0.1

Type RM Length L Ch R = 1 ,1384    ,429,429,429
BEGIN DESCRIPTION:
Stream0129 3.0
END DESCRIPTION:
XS GIS Cut Line= 3
        1994775.     13891125.03        1994825.       13891425.
      1995124.98     13891574.99
#Sta/Elev= 30
  4695.6 1520.97  4698.1 1520.97  4705.7 1515.35  4723.5 1507.33  4728.5 1507.74
  4746.3 1500.77  4776.7 1494.23  4784.3 1490.07  4789.3 1490.37  4817.2 1482.75
  4845.1 1469.74  4867.9 1461.18  4905.9 1454.25    4956 1448.41  5006.1 1444.13
  5006.3 1443.63  5010.1 1444.13  5022.1 1447.25  5044.7 1450.03  5089.2 1454.23
    5132 1461.02  5153.2 1464.67  5164.6 1467.95    5187 1478.46  5223.3 1482.58
  5248.7 1490.05    5282 1501.32  5291.3 1506.58  5321.1    1521  5335.1 1524.31
#Mann= 9 ,-1 , 0
  4695.6      .1       0    4956      .1       0  5006.1     .05       0
  5010.1      .1       0  5044.7      .1       0    5132     .07       0
  5153.2      .1       0  5248.7     .07       0  5291.3      .1       0
Bank Sta=5006.1,5010.1
XS Rating Curve= 0 ,0
Exp/Cntr=0.3,0.1

Type RM Length L Ch R = 1 ,955     ,430,430,430
BEGIN DESCRIPTION:
Stream0129 2.0
END DESCRIPTION:
XS GIS Cut Line= 3
      1994324.99       13891525.        1994475.       13891625.
        1994625.       13891925.
#Sta/Elev= 30
  4819.7 1471.88  4833.2 1469.64  4869.3 1456.62  4878.3 1454.41  4905.3 1450.52
  4927.9 1443.57  4963.9  1435.3  5020.3 1429.28  5020.6 1428.78  5024.3 1429.28
  5042.6 1432.23  5053.1 1433.73  5058.7 1435.84  5075.5 1437.33    5081 1439.06
  5097.8 1440.48  5103.4 1442.01  5120.2 1443.21  5125.8 1444.87  5142.5 1445.35
  5148.1 1446.89  5164.9 1447.96  5178.9 1451.47  5226.4 1460.39    5246 1465.86
  5259.9 1473.09  5268.3 1476.28  5282.3 1477.88  5290.7 1480.15  5335.4  1482.6
#Mann= 5 ,-1 , 0
  4819.7      .1       0  5020.3     .05       0  5024.3      .1       0
  5042.6      .1       0  5226.4     .07       0
Bank Sta=5020.3,5024.3
XS Rating Curve= 0 ,0
Exp/Cntr=0.3,0.1

Type RM Length L Ch R = 1 ,525     ,318,318,318
BEGIN DESCRIPTION:
Stream0129 1.0
END DESCRIPTION:
XS GIS Cut Line= 3
        1994125.     13891724.96        1994125.       13891825.
      1994275.02     13892125.04
#Sta/Elev= 30
  4896.1 1454.28  4898.6 1454.28  4916.1 1450.32  4947.6 1439.84  4956.1 1436.54
  4993.6 1418.94  4999.5 1418.71  5004.5 1416.82  5008.1  1416.7  5008.4  1416.2
  5011.9  1416.2  5012.1  1416.7  5040.9 1420.24  5077.2 1426.15  5116.3 1429.88
  5121.9 1431.35  5130.3 1431.85  5138.7 1431.39  5152.7 1433.79    5175 1440.47
  5183.4 1442.34    5189 1442.74  5219.8 1451.51  5233.7 1453.44  5256.1 1458.91
  5272.9 1463.91  5286.8 1466.45  5295.2 1470.46  5309.2 1473.81  5331.6 1475.16
#Mann= 5 ,-1 , 0
  4896.1     .07       0  4947.6      .1       0  4999.5      .1       0
  5008.1     .05       0  5012.1      .1       0
Bank Sta=5008.1,5012.1
XS Rating Curve= 0 ,0
Exp/Cntr=0.3,0.1

Type RM Length L Ch R = 1 ,207     ,0,0,0
BEGIN DESCRIPTION:
Stream0129 0.0
END DESCRIPTION:
XS GIS Cut Line= 4
      1993980.46      13891561.8      1993900.65      13891946.3
      1993969.55     13892227.48      1994303.73     13892504.71
#Sta/Elev= 30
  4482.3 1479.15  4540.5  1478.9  4587.9 1476.95  4632.9 1471.52  4728.1 1446.55
  4751.1 1443.33  4828.3 1438.84    4875 1438.49  4904.5 1431.58    4912 1427.13
  4917.1 1426.64  4935.4 1418.98  4976.6 1413.46  4984.9 1410.24  4985.2 1409.74
  4988.9 1410.24  5017.8 1421.21  5036.8 1425.88  5078.4 1428.67  5100.2 1432.22
  5131.1 1442.34  5201.9 1448.88  5237.1 1458.67  5282.7 1467.13  5301.5 1472.95
  5328.8 1475.53  5479.6 1488.28  5528.8 1493.38  5571.8 1509.07  5598.7 1515.67
#Mann= 7 ,-1 , 0
  4482.3     .07       0  4540.5      .1       0  4984.9     .05       0
  4988.9      .1       0  5282.7     .07       0  5328.8    .035       0
  5479.6     .07       0
Bank Sta=4984.9,4988.9
XS Rating Curve= 0 ,0
Exp/Cntr=0.3,0.1

Chan Stop Cuts=-1
Use User Specified Reach Order=0
Composite Channel Slope=5