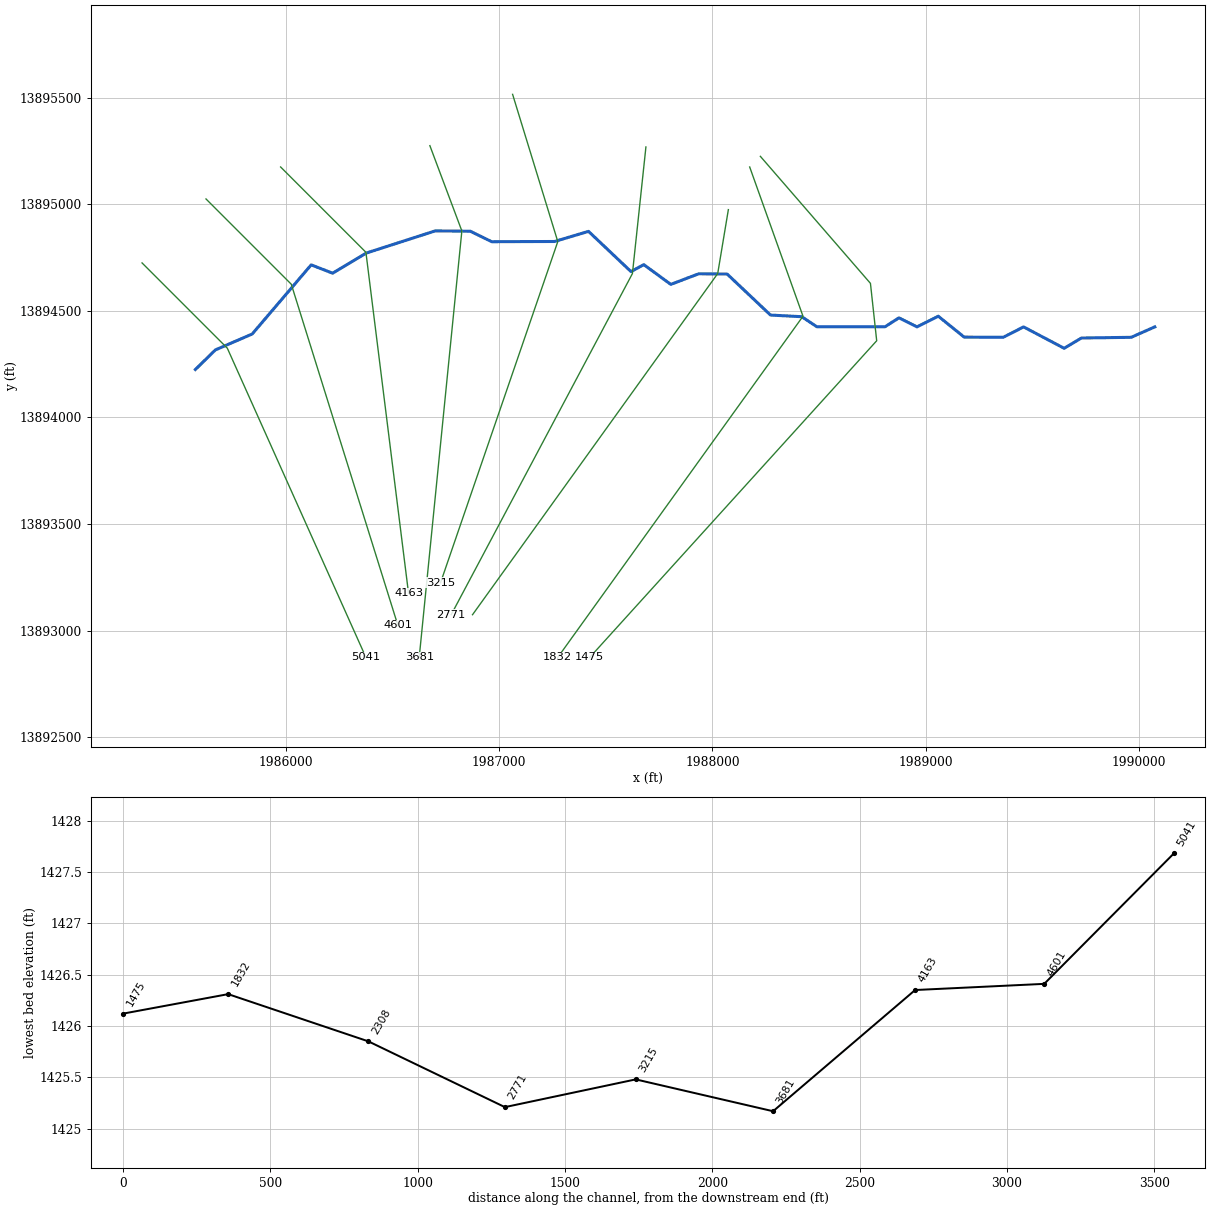
--- Stream0140.prj (project) ---

Proj Title=Stream0140 Base Level Engineering
Current Plan=p01
Default Exp/Contr=0.3,0.1
English Units
Geom File=g01
Flow File=f01
Plan File=p01
BEGIN DESCRIPTION:
Stream0140
END DESCRIPTION:

--- Stream0140.p01 (plan) ---

Plan Title=Multiple Run
Short Identifier=Multiple
Geom File=g01
Flow File=f01
Subcritical Flow
K Sum by GR= 0
Std Step Tol= 0.01
Critical Tol= 0.01
Num of Std Step Trials= 20
Max Error Tol= 0.3
Flow Tol Ratio= 0.001
Split Flow NTrial= 30
Split Flow Tol= 0.02
Split Flow Ratio= 0.02
Log Output Level= 0
Friction Slope Method= 1
Unsteady Friction Slope Method= 2
Unsteady Bridges Friction Slope Method= 1
Parabolic Critical Depth
Global Vel Dist=  1 , 1 , 1
Global Log Level= 0
CheckData=True
Encroach Param= -1, 0, 0, 0
BEGIN DESCRIPTION:
Multiple Run
END DESCRIPTION:

--- Stream0140.f01 (steady flow) ---

Flow Title=Multiple
Number of Profiles=7
Profile Names=10-year,25-year,50-year,1pct_min,100-year,1pct_plu,500-year
River Rch & RM= Stream0140,Reach-1,5041
     934    1538    2094    1378    2749    5484    4691
Boundary for River Rch & Prof#=Stream0140,Reach-1,1
Up Type=0
Dn Type=3
Dn Slope=0.005
Boundary for River Rch & Prof#=Stream0140,Reach-1,2
Up Type=0
Dn Type=3
Dn Slope=0.005
Boundary for River Rch & Prof#=Stream0140,Reach-1,3
Up Type=0
Dn Type=3
Dn Slope=0.005
Boundary for River Rch & Prof#=Stream0140,Reach-1,4
Up Type=0
Dn Type=3
Dn Slope=0.005
Boundary for River Rch & Prof#=Stream0140,Reach-1,5
Up Type=0
Dn Type=3
Dn Slope=0.005
Boundary for River Rch & Prof#=Stream0140,Reach-1,6
Up Type=0
Dn Type=3
Dn Slope=0.005
Boundary for River Rch & Prof#=Stream0140,Reach-1,7
Up Type=0
Dn Type=3
Dn Slope=0.005

--- Stream0140.g01 (geometry) ---

Geom Title=Existing Conditions

River Reach=Stream0140,Reach-1
Reach XY= 30
      1985575.00     13894225.00      1985668.92     13894316.91
      1985841.68     13894391.64      1986118.25     13894715.86
      1986218.87     13894676.84      1986376.58     13894771.17
      1986699.92     13894875.20      1986864.49     13894873.78
      1986964.81     13894824.55      1987259.78     13894825.52
      1987419.11     13894873.04      1987618.33     13894684.30
      1987678.33     13894716.98      1987804.92     13894624.33
      1987935.51     13894673.79      1988069.14     13894672.95
      1988272.55     13894480.47      1988419.06     13894472.73
      1988490.22     13894425.52      1988809.84     13894425.66
      1988875.01     13894467.41      1988959.59     13894425.17
      1989059.66     13894475.04      1989180.86     13894377.07
      1989364.50     13894376.24      1989459.61     13894424.92
      1989650.00     13894324.59      1989730.93     13894372.71
      1989964.54     13894376.12      1990075.00     13894425.00

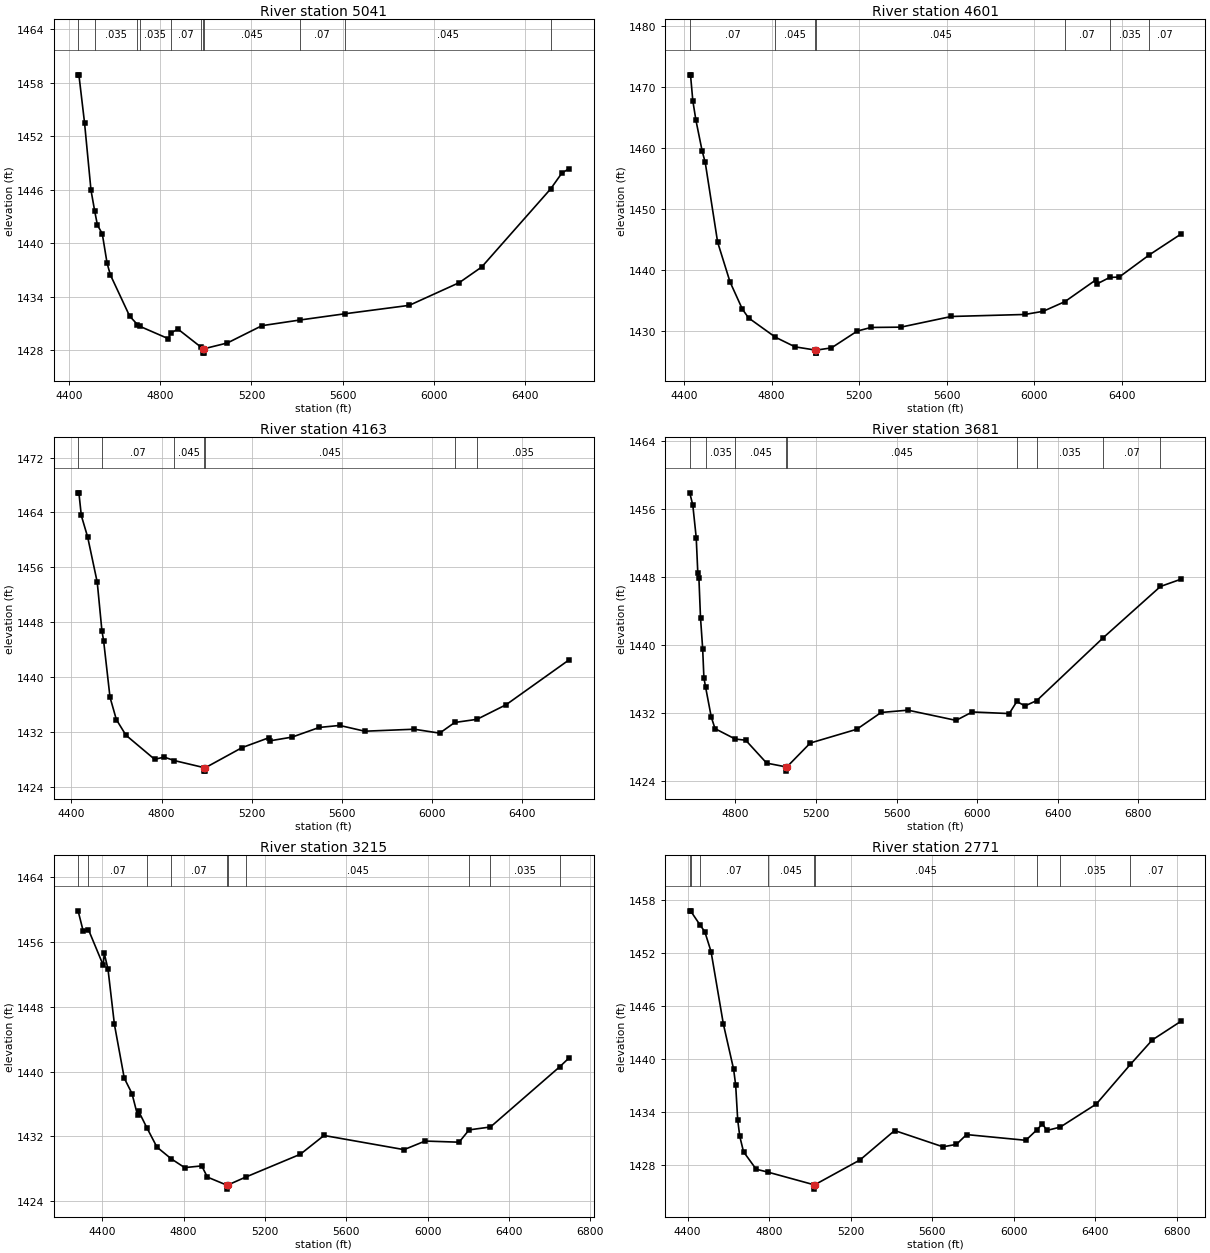
Type RM Length L Ch R = 1,5041,440,440,440
BEGIN DESCRIPTION:
Stream0140 9.0
END DESCRIPTION:
XS GIS Cut Line= 3
      1985325.03     13894724.97      1985725.00     13894325.00
      1986375.02     13892874.97
#Sta/Elev= 30
  4439.4 1458.90  4442.9 1458.90  4467.6 1453.53  4495.9 1445.97  4512.0 1443.65
  4524.2 1442.04  4545.4 1441.08  4566.6 1437.77  4580.8 1436.47  4665.6 1431.83
  4699.9 1430.88  4711.0 1430.68  4835.3 1429.30  4845.8 1429.94  4877.8 1430.37
  4978.6 1428.35  4988.6 1428.18  4988.9 1427.68  4992.9 1427.68  4993.2 1428.18
  5094.4 1428.82  5246.1 1430.76  5411.1 1431.39  5608.5 1432.09  5892.3 1433.04
  6111.9 1435.59  6210.1 1437.34  6512.5 1446.10  6562.0 1447.88  6594.1 1448.38
#Mann=11,-1,0
  4439.4     0.1       0  4512.0   0.035       0  4699.9    0.07       0
  4711.0   0.035       0  4845.8    0.07       0  4978.6   0.045       0
  4988.6   0.045       0  4993.2   0.045       0  5411.1    0.07       0
  5608.5   0.045       0  6512.5    0.07       0
Bank Sta=4988.6,4993.2
Exp/Cntr=0.3,0.1

Type RM Length L Ch R = 1,4601,438,438,438
BEGIN DESCRIPTION:
Stream0140 8.0
END DESCRIPTION:
XS GIS Cut Line= 3
      1985625.00     13895025.00      1986025.00     13894625.00
      1986525.00     13893025.00
#Sta/Elev= 30
  4426.7 1472.05  4430.2 1472.05  4440.8 1467.78  4455.0 1464.59  4483.3 1459.57
  4497.4 1457.68  4554.0 1444.61  4610.6 1438.09  4667.1 1433.61  4695.4 1432.18
  4817.8 1429.02  4907.5 1427.44  5000.5 1426.91  5000.9 1426.41  5004.9 1426.41
  5005.2 1426.91  5073.6 1427.27  5191.5 1430.03  5254.3 1430.62  5390.5 1430.67
  5621.0 1432.42  5956.3 1432.75  6040.1 1433.27  6139.1 1434.85  6279.5 1438.39
  6284.7 1437.74  6343.6 1438.82  6387.4 1438.89  6525.3 1442.54  6668.7 1445.92
#Mann=7,-1,0
  4426.7    0.07       0  4817.8   0.045       0  5000.5   0.045       0
  5005.2   0.045       0  6139.1    0.07       0  6343.6   0.035       0
  6525.3    0.07       0
Bank Sta=5000.5,5005.2
Exp/Cntr=0.3,0.1

Type RM Length L Ch R = 1,4163,482,482,482
BEGIN DESCRIPTION:
Stream0140 7.0
END DESCRIPTION:
XS GIS Cut Line= 3
      1985974.97     13895175.03      1986375.00     13894775.00
      1986575.00     13893174.97
#Sta/Elev= 30
  4429.9 1466.86  4433.5 1466.86  4444.1 1463.56  4472.4 1460.41  4514.8 1453.84
  4535.5 1446.80  4543.1 1445.32  4571.4 1437.11  4599.6 1433.85  4642.1 1431.58
  4769.3 1428.07  4811.8 1428.39  4856.3 1427.89  4989.7 1426.85  4990.0 1426.35
  4994.1 1426.35  4994.5 1426.85  5156.9 1429.77  5275.3 1431.20  5280.3 1430.76
  5378.6 1431.30  5499.5 1432.71  5590.2 1433.00  5701.1 1432.16  5920.3 1432.45
  6033.6 1431.88  6100.3 1433.43  6199.0 1433.89  6328.4 1436.02  6608.1 1442.56
#Mann=7,-1,0
  4429.9     0.1       0  4535.5    0.07       0  4856.3   0.045       0
  4989.7   0.045       0  4994.5   0.045       0  6100.3    0.07       0
  6199.0   0.035       0
Bank Sta=4989.7,4994.5
Exp/Cntr=0.3,0.1

Type RM Length L Ch R = 1,3681,466,466,466
BEGIN DESCRIPTION:
Stream0140 6.0
END DESCRIPTION:
XS GIS Cut Line= 3
      1986674.99     13895275.03      1986825.00     13894875.00
      1986625.00     13892875.01
#Sta/Elev= 30
  4573.2 1457.86  4588.4 1456.42  4605.3 1452.61  4613.3 1448.43  4618.6 1447.91
  4626.6 1443.21  4637.3 1439.57  4643.5 1436.14  4652.1 1435.01  4680.0 1431.53
  4698.7 1430.16  4799.0 1428.94  4850.9 1428.80  4955.0 1426.11  5050.8 1425.67
  5051.1 1425.17  5055.6 1425.67  5171.3 1428.47  5402.4 1430.09  5523.0 1432.06
  5656.2 1432.33  5894.9 1431.13  5975.3 1432.12  6158.7 1431.93  6196.4 1433.35
  6236.6 1432.83  6295.6 1433.46  6626.1 1440.86  6909.1 1446.86  7010.4 1447.71
#Mann=9,-1,0
  4573.2    0.07       0  4652.1   0.035       0  4799.0   0.045       0
  5050.8   0.045       0  5055.6   0.045       0  6196.4    0.07       0
  6295.6   0.035       0  6626.1    0.07       0  6909.1   0.035       0
Bank Sta=5050.8,5055.6
Exp/Cntr=0.3,0.1

Type RM Length L Ch R = 1,3215,444,444,444
BEGIN DESCRIPTION:
Stream0140 5.0
END DESCRIPTION:
XS GIS Cut Line= 3
      1987063.03     13895515.65      1987275.00     13894825.00
      1986725.01     13893225.03
#Sta/Elev= 30
  4281.7 1459.87  4307.0 1457.34  4332.3 1457.56  4405.2 1453.15  4410.4 1454.62
  4428.8 1452.64  4460.2 1445.84  4508.6 1439.20  4546.6 1437.29  4574.1 1434.59
  4579.3 1435.10  4619.4 1433.08  4669.4 1430.67  4739.9 1429.22  4805.4 1428.14
  4889.6 1428.35  4917.1 1426.97  5012.0 1425.98  5012.4 1425.48  5016.9 1425.98
  5106.7 1426.98  5374.2 1429.79  5490.6 1432.11  5884.0 1430.36  5987.6 1431.42
  6154.6 1431.28  6203.7 1432.80  6308.9 1433.16  6648.9 1440.59  6696.0 1441.71
#Mann=10,-1,0
  4281.7   0.035       0  4332.3    0.07       0  4619.4   0.035       0
  4739.9    0.07       0  5012.0    0.05       0  5016.9    0.07       0
  5106.7   0.045       0  6203.7    0.07       0  6308.9   0.035       0
  6648.9    0.07       0
Bank Sta=5012,5016.9
Exp/Cntr=0.3,0.1

Type RM Length L Ch R = 1,2771,463,463,463
BEGIN DESCRIPTION:
Stream0140 4.0
END DESCRIPTION:
XS GIS Cut Line= 3
      1987688.32     13895268.99      1987625.00     13894675.00
      1986775.01     13893075.02
#Sta/Elev= 30
  4410.4 1456.79  4414.3 1456.79  4459.6 1455.23  4484.3 1454.42  4515.0 1452.16
  4575.3 1443.95  4625.6 1438.82  4635.7 1437.02  4645.7 1433.06  4655.8 1431.20
  4674.2 1429.45  4736.2 1427.47  4792.2 1427.15  5019.1 1425.71  5019.5 1425.21
  5024.0 1425.71  5245.5 1428.52  5415.4 1431.86  5652.7 1430.01  5718.6 1430.29
  5768.3 1431.40  6059.0 1430.75  6114.6 1431.97  6140.1 1432.61  6162.8 1431.87
  6227.9 1432.25  6405.0 1434.87  6572.3 1439.37  6679.5 1442.14  6819.5 1444.25
#Mann=9,-1,0
  4410.4    0.07       0  4414.3   0.045       0  4459.6    0.07       0
  4792.2   0.045       0  5019.1   0.045       0  5024.0   0.045       0
  6114.6    0.07       0  6227.9   0.035       0  6572.3    0.07       0
Bank Sta=5019.1,5024
Exp/Cntr=0.3,0.1

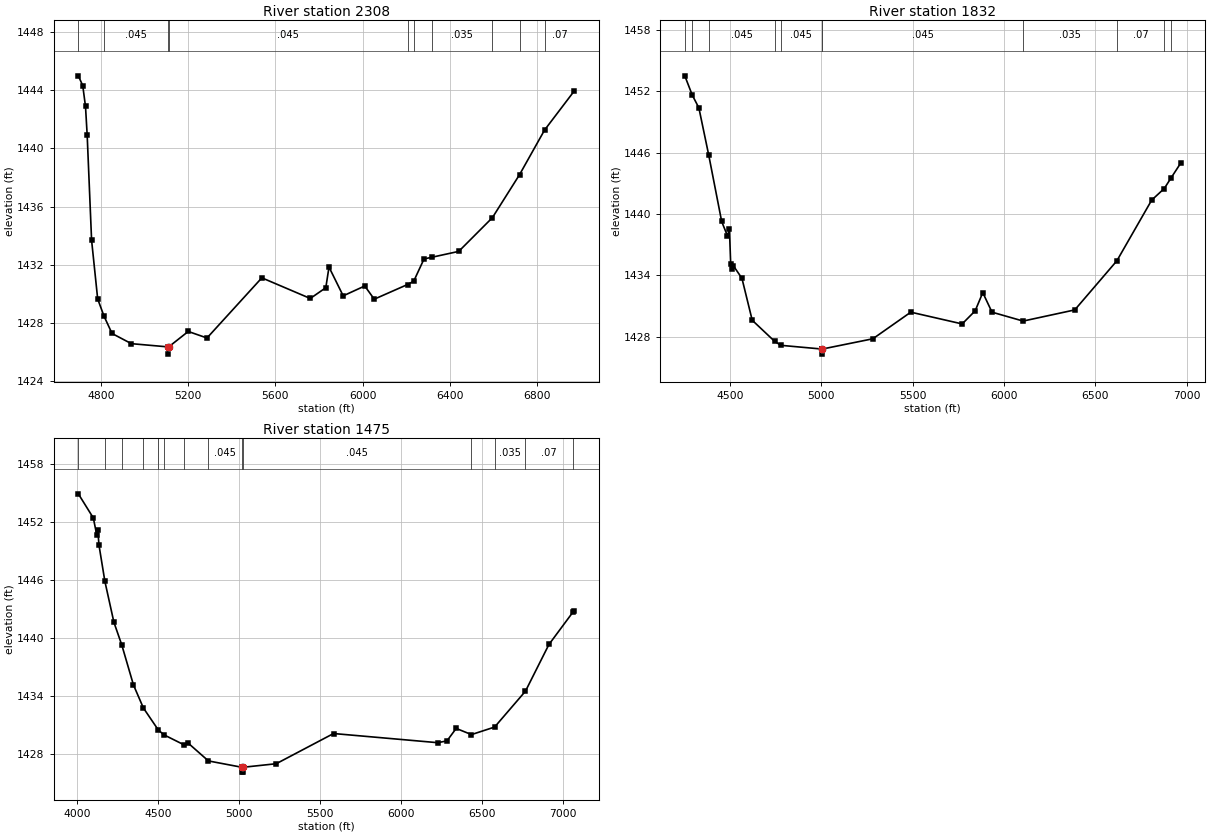
Type RM Length L Ch R = 1,2308,476,476,476
BEGIN DESCRIPTION:
Stream0140 3.0
END DESCRIPTION:
XS GIS Cut Line= 3
      1988074.99     13894974.96      1988025.00     13894675.00
      1986875.00     13893075.00
#Sta/Elev= 30
  4696.4 1445.00  4716.6 1444.33  4729.3 1442.89  4736.9 1440.94  4757.2 1433.69
  4785.1 1429.65  4814.3 1428.46  4851.0 1427.27  4939.7 1426.57  5106.0 1426.35
  5106.4 1425.85  5111.0 1426.35  5200.6 1427.41  5286.6 1426.96  5538.2 1431.10
  5760.4 1429.68  5831.6 1430.42  5846.3 1431.84  5911.4 1429.86  6010.3 1430.54
  6053.8 1429.63  6206.6 1430.64  6235.0 1430.87  6282.2 1432.40  6319.6 1432.52
  6441.4 1432.92  6595.8 1435.24  6720.4 1438.20  6835.2 1441.27  6970.9 1443.95
#Mann=10,-1,0
  4696.4    0.07       0  4814.3   0.045       0  5106.0   0.045       0
  5111.0   0.045       0  6206.6   0.035       0  6235.0    0.07       0
  6319.6   0.035       0  6595.8    0.07       0  6720.4   0.035       0
  6835.2    0.07       0
Bank Sta=5106,5111
Exp/Cntr=0.3,0.1

Type RM Length L Ch R = 1,1832,357,357,357
BEGIN DESCRIPTION:
Stream0140 2.0
END DESCRIPTION:
XS GIS Cut Line= 3
      1988174.99     13895175.02      1988425.00     13894475.00
      1987275.02     13892875.03
#Sta/Elev= 30
  4252.4 1453.50  4293.2 1451.62  4329.4 1450.37  4383.2 1445.77  4454.2 1439.27
  4486.0 1437.86  4496.7 1438.50  4503.6 1435.10  4508.9 1434.60  4517.9 1434.95
  4565.1 1433.72  4621.4 1429.62  4743.4 1427.57  4778.2 1427.17  5000.6 1426.81
  5000.9 1426.31  5005.6 1426.81  5281.8 1427.81  5489.3 1430.41  5770.4 1429.26
  5841.6 1430.54  5883.3 1432.32  5933.7 1430.41  6104.1 1429.54  6386.7 1430.63
  6617.2 1435.43  6807.8 1441.36  6876.5 1442.49  6914.7 1443.55  6966.1 1444.96
#Mann=11,-1,0
  4252.4   0.035       0  4293.2    0.07       0  4383.2   0.045       0
  4743.4    0.07       0  4778.2   0.045       0  5000.6   0.045       0
  5005.6   0.045       0  6104.1   0.035       0  6617.2    0.07       0
  6876.5   0.035       0  6914.7    0.07       0
Bank Sta=5000.6,5005.6
Exp/Cntr=0.3,0.1

Type RM Length L Ch R = 1,1475,0,0,0
BEGIN DESCRIPTION:
Stream0140 1.0
END DESCRIPTION:
XS GIS Cut Line= 4
      1988225.02     13895224.97      1988741.40     13894629.15
      1988770.72     13894359.94      1987424.97     13892874.97
#Sta/Elev= 30
  4005.9 1454.96  4098.5 1452.46  4119.4 1450.73  4126.0 1451.20  4133.6 1449.63
  4169.9 1445.89  4225.7 1441.65  4274.3 1439.30  4346.4 1435.16  4407.7 1432.77
  4500.0 1430.49  4534.4 1429.99  4661.1 1428.93  4686.3 1429.10  4809.7 1427.28
  5017.3 1426.62  5017.7 1426.12  5022.0 1426.12  5022.3 1426.62  5228.5 1426.99
  5582.7 1430.12  6226.7 1429.17  6283.5 1429.36  6340.3 1430.65  6434.7 1430.01
  6577.7 1430.79  6768.4 1434.51  6913.4 1439.35  7060.7 1442.68  7069.2 1442.80
#Mann=14,-1,0
  4005.9   0.035       0  4169.9   0.045       0  4274.3   0.035       0
  4407.7    0.07       0  4500.0   0.035       0  4534.4   0.045       0
  4661.1    0.07       0  4809.7   0.045       0  5017.3   0.045       0
  5022.3   0.045       0  6434.7    0.07       0  6577.7   0.035       0
  6768.4    0.07       0  7060.7   0.035       0
Bank Sta=5017.3,5022.3
Exp/Cntr=0.3,0.1

Chan Stop Cuts=-1