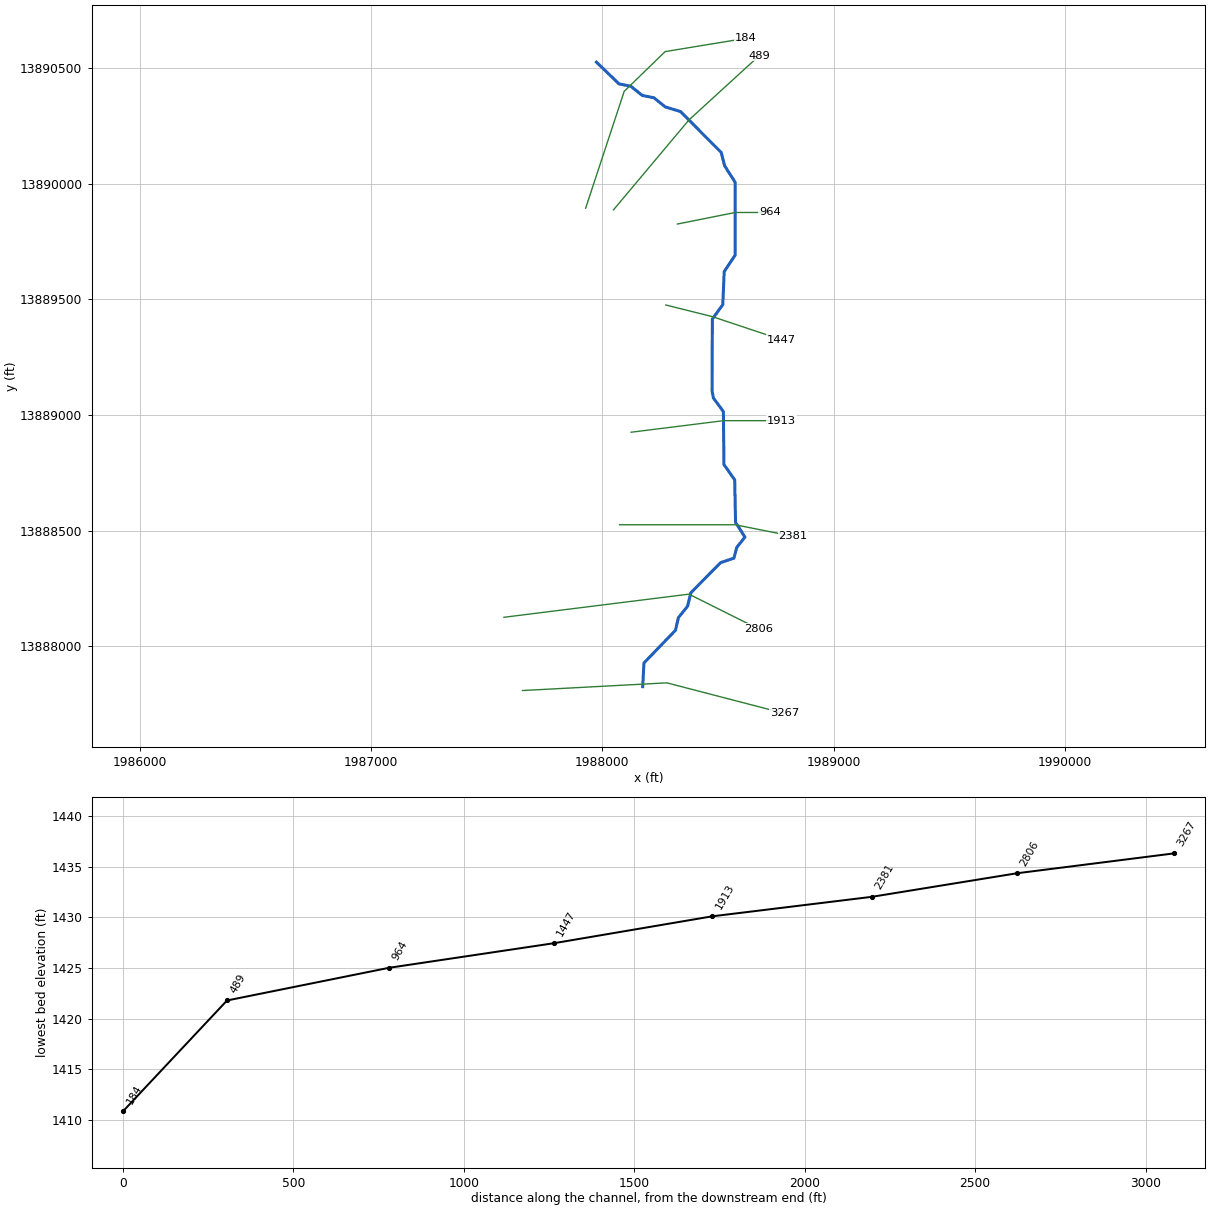
--- Stream0173.prj (project) ---

Proj Title=Stream0173 Base Level Engineering
Current Plan=p01
Default Exp/Contr=0.3,0.1
English Units
Geom File=g01
Flow File=f01
Plan File=p01
BEGIN DESCRIPTION:
Stream0173
END DESCRIPTION:

--- Stream0173.p01 (plan) ---

Plan Title=Multiple Run
Short Identifier=Multiple
Geom File=g01
Flow File=f01
Subcritical Flow
K Sum by GR= 0
Std Step Tol= 0.01
Critical Tol= 0.01
Num of Std Step Trials= 20
Max Error Tol= 0.3
Flow Tol Ratio= 0.001
Split Flow NTrial= 30
Split Flow Tol= 0.02
Split Flow Ratio= 0.02
Log Output Level= 0
Friction Slope Method= 1
Unsteady Friction Slope Method= 2
Unsteady Bridges Friction Slope Method= 1
Parabolic Critical Depth
Global Vel Dist=  1 , 1 , 1
Global Log Level= 0
CheckData=True
Encroach Param= -1, 0, 0, 0
BEGIN DESCRIPTION:
Multiple Run
END DESCRIPTION:

--- Stream0173.f01 (steady flow) ---

Flow Title=Multiple
Number of Profiles=7
Profile Names=10-year,25-year,50-year,1pct_min,100-year,1pct_plu,500-year
River Rch & RM= Stream0173,Reach-1,3267
     671    1102    1498     988    1972    3934    3376
Boundary for River Rch & Prof#=Stream0173,Reach-1,1
Up Type=0
Dn Type=3
Dn Slope=0.005
Boundary for River Rch & Prof#=Stream0173,Reach-1,2
Up Type=0
Dn Type=3
Dn Slope=0.005
Boundary for River Rch & Prof#=Stream0173,Reach-1,3
Up Type=0
Dn Type=3
Dn Slope=0.005
Boundary for River Rch & Prof#=Stream0173,Reach-1,4
Up Type=0
Dn Type=3
Dn Slope=0.005
Boundary for River Rch & Prof#=Stream0173,Reach-1,5
Up Type=0
Dn Type=3
Dn Slope=0.005
Boundary for River Rch & Prof#=Stream0173,Reach-1,6
Up Type=0
Dn Type=3
Dn Slope=0.005
Boundary for River Rch & Prof#=Stream0173,Reach-1,7
Up Type=0
Dn Type=3
Dn Slope=0.005

--- Stream0173.g01 (geometry) ---

Geom Title=Existing Conditions

River Reach=Stream0173,Reach-1
Reach XY= 30
      1988175.00     13887825.00      1988180.35     13887927.50
      1988316.86     13888068.94      1988329.19     13888123.26
      1988368.90     13888172.81      1988383.14     13888231.06
      1988512.02     13888361.28      1988569.44     13888380.62
      1988581.55     13888426.95      1988616.97     13888471.65
      1988576.38     13888535.44      1988572.74     13888719.06
      1988526.22     13888785.50      1988523.78     13889014.50
      1988480.75     13889072.67      1988474.64     13889104.85
      1988476.22     13889414.50      1988521.21     13889476.57
      1988527.27     13889619.06      1988574.48     13889690.22
      1988574.94     13890004.97      1988529.22     13890076.75
      1988514.24     13890134.68      1988338.21     13890311.38
      1988272.81     13890331.10      1988223.28     13890370.84
      1988172.80     13890381.08      1988123.27     13890420.82
      1988072.68     13890430.79      1987975.00     13890525.00

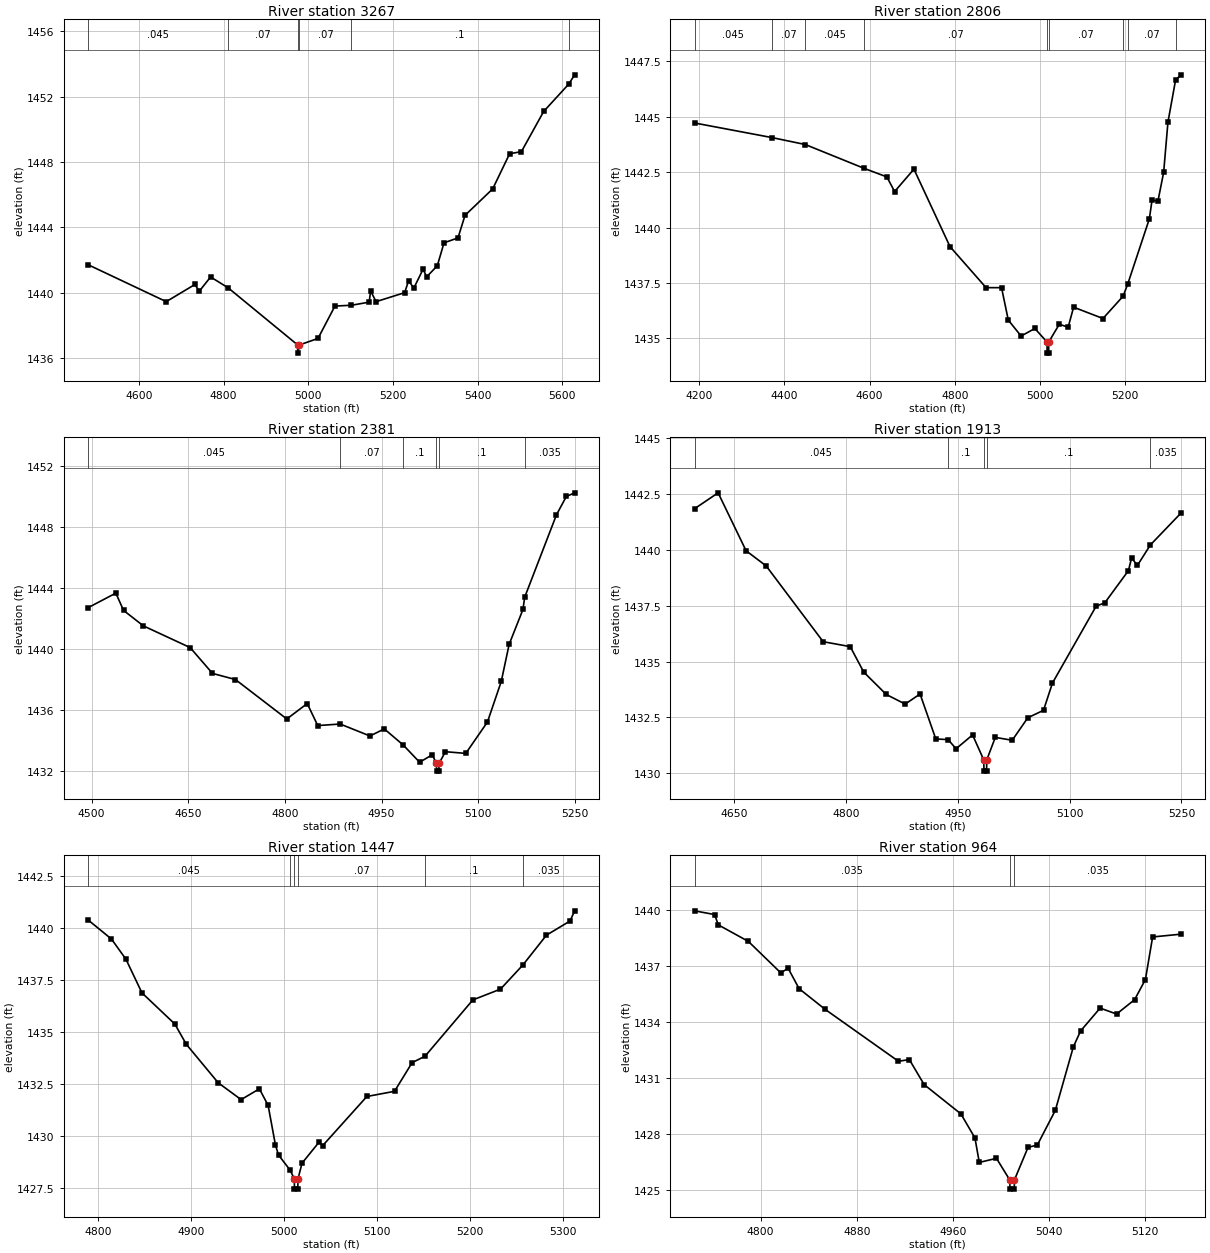
Type RM Length L Ch R = 1,3267,461,461,461
BEGIN DESCRIPTION:
Stream0173 7.0
END DESCRIPTION:
XS GIS Cut Line= 3
      1987655.35     13887808.33      1988279.35     13887841.60
      1988787.09     13887709.62
#Sta/Elev= 30
  4479.7 1441.71  4664.3 1439.45  4732.0 1440.50  4742.4 1440.09  4769.1 1440.96
  4810.4 1440.30  4974.8 1436.80  4975.0 1436.30  4978.8 1436.80  5022.9 1437.20
  5062.9 1439.18  5102.0 1439.23  5143.9 1439.42  5147.0 1440.11  5160.1 1439.45
  5227.6 1440.00  5236.9 1440.73  5249.3 1440.28  5271.0 1441.43  5279.7 1440.97
  5304.8 1441.65  5320.6 1443.05  5353.6 1443.35  5370.2 1444.73  5435.6 1446.35
  5475.6 1448.50  5503.5 1448.63  5556.1 1451.09  5615.2 1452.76  5629.2 1453.33
#Mann=6,-1,0
  4479.7   0.045       0  4810.4    0.07       0  4974.8    0.05       0
  4978.8    0.07       0  5102.0     0.1       0  5615.2   0.035       0
Bank Sta=4974.8,4978.8
Exp/Cntr=0.3,0.1

Type RM Length L Ch R = 1,2806,425,425,425
BEGIN DESCRIPTION:
Stream0173 6.0
END DESCRIPTION:
XS GIS Cut Line= 3
      1987575.03     13888125.00      1988375.00     13888225.00
      1988675.00     13888075.00
#Sta/Elev= 30
  4189.5 1444.71  4371.7 1444.05  4449.2 1443.74  4588.1 1442.66  4640.7 1442.28
  4658.9 1441.62  4704.2 1442.63  4788.8 1439.14  4873.5 1437.29  4909.8 1437.29
  4925.6 1435.83  4955.7 1435.11  4988.0 1435.45  5016.5 1434.84  5016.8 1434.34
  5020.3 1434.34  5020.5 1434.84  5045.3 1435.64  5066.1 1435.51  5078.9 1436.41
  5147.8 1435.90  5195.2 1436.91  5206.2 1437.47  5256.6 1440.39  5262.9 1441.23
  5276.8 1441.19  5290.2 1442.49  5300.2 1444.74  5318.2 1446.65  5331.1 1446.88
#Mann=9,-1,0
  4189.5   0.045       0  4371.7    0.07       0  4449.2   0.045       0
  4588.1    0.07       0  5016.5    0.05       0  5020.5    0.07       0
  5195.2     0.1       0  5206.2    0.07       0  5318.2     0.1       0
Bank Sta=5016.5,5020.5
Exp/Cntr=0.3,0.1

Type RM Length L Ch R = 1,2381,468,468,468
BEGIN DESCRIPTION:
Stream0173 5.0
END DESCRIPTION:
XS GIS Cut Line= 3
      1988075.02     13888525.00      1988575.00     13888525.00
      1988824.97     13888475.01
#Sta/Elev= 30
  4494.6 1442.71  4537.6 1443.66  4549.6 1442.53  4580.3 1441.52  4652.9 1440.10
  4687.6 1438.41  4723.2 1438.01  4802.9 1435.43  4834.6 1436.44  4850.9 1435.00
  4885.7 1435.10  4931.9 1434.32  4954.2 1434.78  4983.5 1433.73  5009.0 1432.60
  5028.6 1433.09  5035.1 1432.52  5035.3 1432.02  5038.8 1432.02  5039.1 1432.52
  5049.0 1433.29  5080.6 1433.18  5114.2 1435.23  5135.7 1437.89  5147.9 1440.31
  5169.3 1442.59  5172.1 1443.40  5221.3 1448.78  5236.6 1449.98  5249.5 1450.22
#Mann=6,-1,0
  4494.6   0.045       0  4885.7    0.07       0  4983.5     0.1       0
  5035.1    0.05       0  5039.1     0.1       0  5172.1   0.035       0
Bank Sta=5035.1,5039.1
Exp/Cntr=0.3,0.1

Type RM Length L Ch R = 1,1913,466,466,466
BEGIN DESCRIPTION:
Stream0173 4.0
END DESCRIPTION:
XS GIS Cut Line= 3
      1988125.01     13888925.00      1988525.00     13888975.00
      1988775.00     13888975.00
#Sta/Elev= 30
  4596.5 1441.84  4628.1 1442.55  4665.6 1439.96  4692.6 1439.28  4769.1 1435.89
  4805.4 1435.67  4823.6 1434.53  4853.8 1433.53  4879.2 1433.10  4899.2 1433.55
  4920.3 1431.54  4936.9 1431.51  4947.5 1431.10  4969.7 1431.72  4984.7 1430.60
  4985.0 1430.10  4988.5 1430.10  4988.7 1430.60  5000.2 1431.61  5022.9 1431.48
  5043.9 1432.49  5064.9 1432.82  5076.9 1434.04  5135.6 1437.48  5147.2 1437.63
  5178.9 1439.07  5183.2 1439.64  5190.9 1439.30  5208.4 1440.22  5249.6 1441.65
#Mann=5,-1,0
  4596.5   0.045       0  4936.9     0.1       0  4984.7    0.05       0
  4988.7     0.1       0  5208.4   0.035       0
Bank Sta=4984.7,4988.7
Exp/Cntr=0.3,0.1

Type RM Length L Ch R = 1,1447,483,483,483
BEGIN DESCRIPTION:
Stream0173 3.0
END DESCRIPTION:
XS GIS Cut Line= 3
      1988274.98     13889475.00      1988475.00     13889425.00
      1988775.00     13889325.00
#Sta/Elev= 30
  4789.7 1440.40  4814.8 1439.48  4830.3 1438.51  4847.5 1436.89  4882.8 1435.39
  4895.2 1434.41  4929.4 1432.56  4954.0 1431.75  4973.6 1432.27  4983.0 1431.47
  4990.9 1429.55  4994.2 1429.08  5006.5 1428.36  5011.1 1427.94  5011.3 1427.44
  5014.8 1427.44  5015.1 1427.94  5019.4 1428.69  5038.0 1429.72  5041.5 1429.53
  5089.0 1431.90  5118.7 1432.15  5137.6 1433.53  5151.5 1433.84  5202.8 1436.55
  5232.5 1437.07  5256.5 1438.23  5281.9 1439.67  5307.2 1440.35  5312.1 1440.84
#Mann=6,-1,0
  4789.7   0.045       0  5006.5    0.07       0  5011.1   0.045       0
  5015.1    0.07       0  5151.5     0.1       0  5256.5   0.035       0
Bank Sta=5011.1,5015.1
Exp/Cntr=0.3,0.1

Type RM Length L Ch R = 1,964,475,475,475
BEGIN DESCRIPTION:
Stream0173 2.0
END DESCRIPTION:
XS GIS Cut Line= 3
      1988324.98     13889825.00      1988575.00     13889875.00
      1988725.03     13889875.00
#Sta/Elev= 30
  4745.0 1439.93  4761.7 1439.73  4764.7 1439.18  4789.8 1438.29  4816.7 1436.61
  4822.9 1436.85  4832.0 1435.76  4853.7 1434.65  4914.7 1431.87  4923.8 1431.96
  4936.1 1430.62  4966.7 1429.05  4978.4 1427.76  4982.0 1426.45  4996.3 1426.67
  5007.3 1425.52  5007.6 1425.02  5011.1 1425.02  5011.3 1425.52  5022.6 1427.26
  5030.3 1427.38  5045.3 1429.24  5060.3 1432.64  5066.3 1433.49  5082.6 1434.72
  5096.3 1434.40  5111.3 1435.17  5120.3 1436.25  5126.3 1438.53  5150.0 1438.68
#Mann=3,-1,0
  4745.0   0.035       0  5007.3   0.035       0  5011.3   0.035       0
Bank Sta=5007.3,5011.3
Exp/Cntr=0.3,0.1

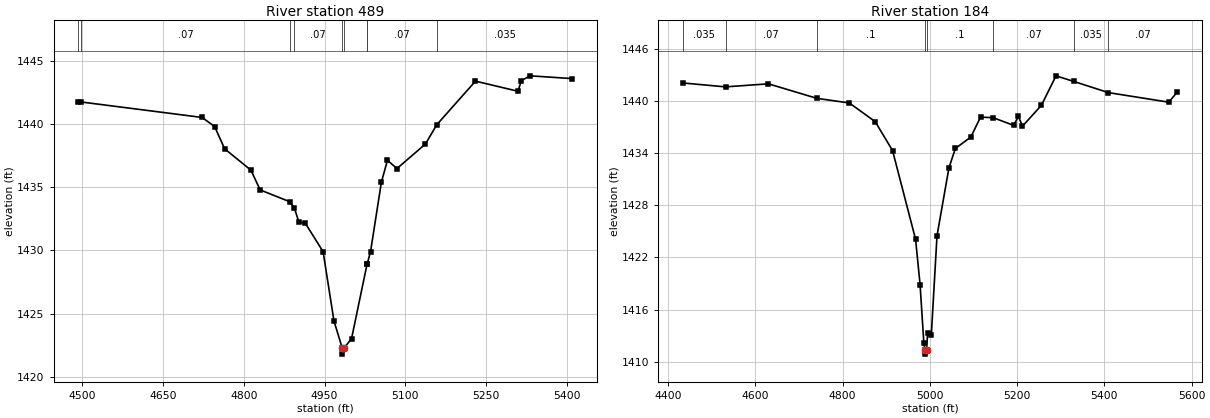
Type RM Length L Ch R = 1,489,305,305,305
BEGIN DESCRIPTION:
Stream0173 1.0
END DESCRIPTION:
XS GIS Cut Line= 3
      1988048.72     13889886.30      1988375.00     13890275.00
      1988678.33     13890552.34
#Sta/Elev= 30
  4492.3 1441.70  4498.1 1441.73  4722.5 1440.51  4745.8 1439.79  4764.4 1438.03
  4813.3 1436.34  4830.4 1434.78  4885.3 1433.85  4893.9 1433.37  4902.3 1432.24
  4914.4 1432.14  4947.4 1429.90  4967.6 1424.42  4982.8 1422.30  4983.0 1421.80
  4986.8 1422.30  5000.3 1423.03  5029.0 1428.89  5029.5 1428.95  5035.6 1429.91
  5055.8 1435.41  5067.0 1437.12  5084.7 1436.47  5137.6 1438.41  5158.8 1439.94
  5230.6 1443.38  5309.6 1442.58  5315.9 1443.43  5332.2 1443.80  5410.8 1443.58
#Mann=9,-1,0
  4492.3   0.035       0  4498.1    0.07       0  4885.3     0.1       0
  4893.9    0.07       0  4982.8    0.05       0  4986.8    0.07       0
  5029.0     0.1       0  5029.5    0.07       0  5158.8   0.035       0
Bank Sta=4982.8,4986.8
Exp/Cntr=0.3,0.1

Type RM Length L Ch R = 1,184,0,0,0
BEGIN DESCRIPTION:
Stream0173 0.0
END DESCRIPTION:
XS GIS Cut Line= 4
      1987928.36     13889893.41      1988095.02     13890398.60
      1988272.10     13890570.48      1988621.08     13890627.77
#Sta/Elev= 30
  4434.2 1442.06  4531.9 1441.61  4630.2 1441.96  4741.2 1440.29  4815.5 1439.76
  4874.9 1437.61  4914.6 1434.29  4967.4 1424.08  4977.7 1418.88  4986.3 1412.18
  4988.8 1411.38  4989.1 1410.88  4992.8 1411.38  4994.9 1413.27  5003.5 1413.11
  5016.5 1424.49  5043.8 1432.29  5058.6 1434.53  5094.0 1435.84  5116.2 1438.13
  5145.1 1438.07  5192.3 1437.18  5202.9 1438.22  5212.4 1437.09  5255.7 1439.49
  5289.2 1442.88  5329.6 1442.24  5409.2 1440.95  5547.6 1439.85  5566.6 1440.99
#Mann=8,-1,0
  4434.2   0.035       0  4531.9    0.07       0  4741.2     0.1       0
  4988.8    0.05       0  4992.8     0.1       0  5145.1    0.07       0
  5329.6   0.035       0  5409.2    0.07       0
Bank Sta=4988.8,4992.8
Exp/Cntr=0.3,0.1

Chan Stop Cuts=-1