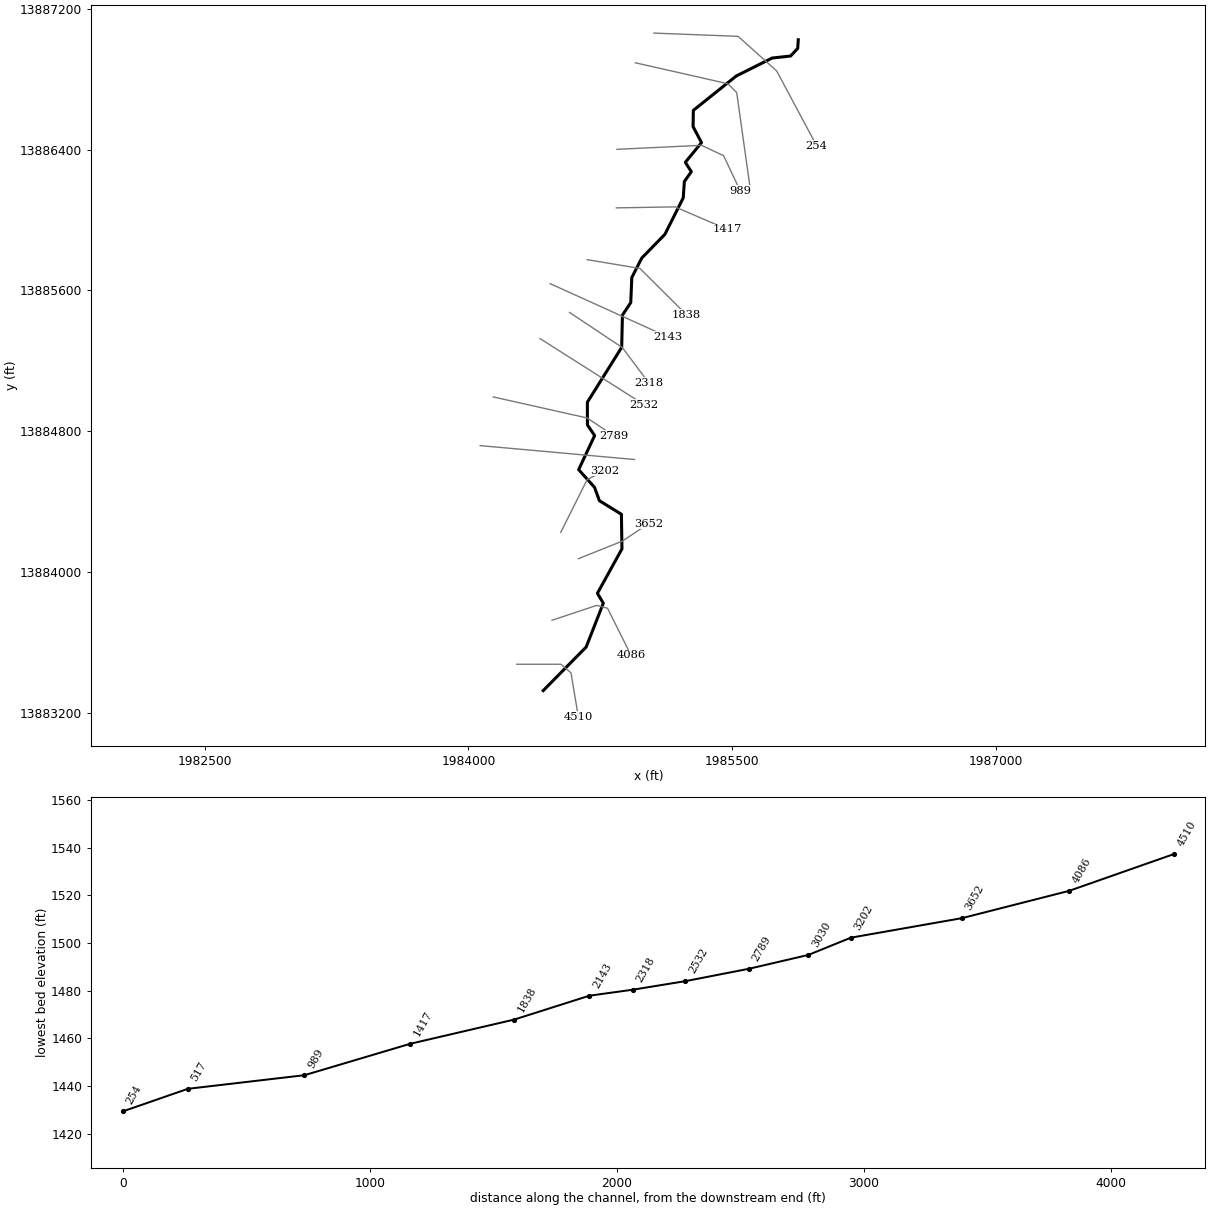
--- Stream0176.prj (project) ---

Proj Title=Stream0176 Base Level Engineering
Current Plan=p01
Default Exp/Contr=0.3,0.1
English Units
Geom File=g01
Flow File=f01
Plan File=p01
Y Axis Title=Elevation
X Axis Title(PF)=Main Channel Distance
X Axis Title(XS)=Station
BEGIN DESCRIPTION:
Stream0176
END DESCRIPTION:
DSS Export Rating Curves= 0
DSS Export Rating Curve Sorted= 0
DSS Export Volume Flow Curves= 0
DXF OffsetX= 0
DXF OffsetY= 0
DXF ScaleX= 1
DXF ScaleY= 10

--- Stream0176.p01 (plan) ---

Plan Title=Multiple Run
Short Identifier=Multiple
Geom File=g01
Flow File=f01
Subcritical Flow
K Sum by GR= 0
Std Step Tol= 0.01
Critical Tol= 0.01
Num of Std Step Trials= 20
Max Error Tol= 0.3
Flow Tol Ratio= 0.001
Split Flow NTrial= 30
Split Flow Tol= 0.02
Split Flow Ratio= 0.02
Log Output Level= 0
Friction Slope Method= 1
Unsteady Friction Slope Method= 2
Unsteady Bridges Friction Slope Method= 1
Parabolic Critical Depth
Global Vel Dist=  1 , 1 , 1
Global Log Level= 0
CheckData=True
Encroach Param= -1, 0, 0, 0
BEGIN DESCRIPTION:
Multiple Run
END DESCRIPTION:

--- Stream0176.f01 (steady flow) ---

Flow Title=Multiple
Number of Profiles=7
Profile Names=10-year,25-year,50-year,1pct_min,100-year,1pct_plu,500-year
River Rch & RM= Stream0176,Reach-1,4510
     724    1215    1679    1128    2251    4491    3996
Boundary for River Rch & Prof#=Stream0176,Reach-1,1
Up Type=0
Dn Type=3
Dn Slope=0.005
Boundary for River Rch & Prof#=Stream0176,Reach-1,2
Up Type=0
Dn Type=3
Dn Slope=0.005
Boundary for River Rch & Prof#=Stream0176,Reach-1,3
Up Type=0
Dn Type=3
Dn Slope=0.005
Boundary for River Rch & Prof#=Stream0176,Reach-1,4
Up Type=0
Dn Type=3
Dn Slope=0.005
Boundary for River Rch & Prof#=Stream0176,Reach-1,5
Up Type=0
Dn Type=3
Dn Slope=0.005
Boundary for River Rch & Prof#=Stream0176,Reach-1,6
Up Type=0
Dn Type=3
Dn Slope=0.005
Boundary for River Rch & Prof#=Stream0176,Reach-1,7
Up Type=0
Dn Type=3
Dn Slope=0.005

--- Stream0176.g01 (geometry) ---

Geom Title=Existing Conditions
Program Version=4.10

River Reach=Stream0176      ,Reach-1
Reach XY= 30
        1984425.       13883325.      1984669.17      13883572.7
      1984766.72     13883821.78      1984733.24     13883878.23
      1984872.76     13884130.93      1984869.64      13884327.7
      1984744.64     13884404.53      1984716.81     13884481.02
      1984626.62     13884581.04      1984717.47     13884774.99
      1984676.37     13884835.44      1984676.19      13884964.5
      1984871.25     13885276.55      1984875.52     13885459.78
      1984922.73     13885530.94      1984928.76     13885673.44
      1984985.76     13885784.68      1985116.86     13885918.94
      1985221.18     13886126.59      1985227.54     13886219.11
       1985267.2      13886275.1      1985233.01     13886328.33
      1985325.04     13886440.34      1985277.19     13886530.97
      1985278.46     13886623.52      1985522.71     13886819.15
      1985726.59     13886921.17      1985831.45     13886932.64
      1985871.88     13886975.99        1985875.       13887025.

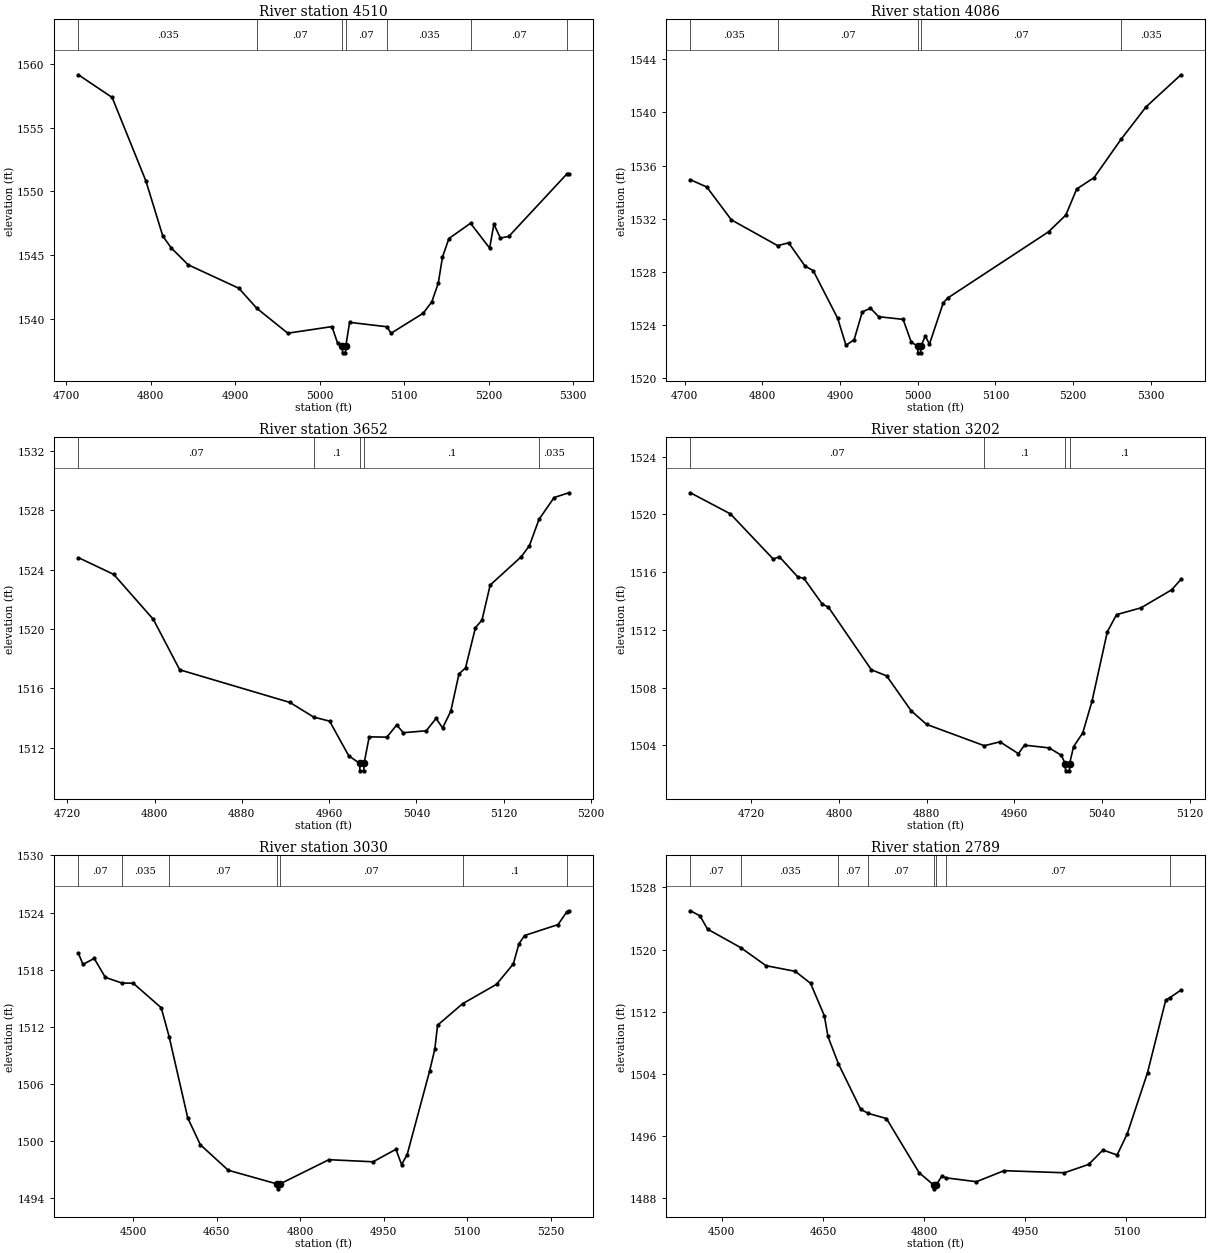
Type RM Length L Ch R = 1 ,4510    ,424,424,424
BEGIN DESCRIPTION:
Stream0176 10.0
END DESCRIPTION:
XS GIS Cut Line= 4
      1984274.99       13883475.      1984526.07       13883475.
      1984583.18     13883425.93      1984625.01     13883174.97
#Sta/Elev= 30
  4714.2 1559.15  4754.2 1557.37  4794.2 1550.81  4814.2 1546.49  4824.2 1545.56
  4844.2 1544.24  4904.2  1542.4  4925.6 1540.82  4962.2 1538.87  5014.5 1539.39
  5021.1  1538.1  5026.8 1537.83    5027 1537.33  5030.5 1537.33  5030.8 1537.83
  5035.4 1539.72  5079.3 1539.38  5084.6 1538.87  5122.6 1540.44  5132.8 1541.34
  5140.4  1542.8  5145.4 1544.85    5153  1546.3  5178.6  1547.5  5201.2 1545.55
  5206.3 1547.43  5213.9 1546.34    5224 1546.47    5293 1551.39    5295 1551.39
#Mann= 7 ,-1 , 0
  4714.2    .035       0  4925.6     .07       0  5026.8     .05       0
  5030.8     .07       0  5079.3    .035       0  5178.6     .07       0
    5293    .035       0
Bank Sta=5026.8,5030.8
XS Rating Curve= 0 ,0
Exp/Cntr=0.3,0.1

Type RM Length L Ch R = 1 ,4086    ,434,434,434
BEGIN DESCRIPTION:
Stream0176 9.0
END DESCRIPTION:
XS GIS Cut Line= 4
      1984475.01       13883725.      1984728.88     13883809.63
      1984790.84     13883793.31      1984925.02     13883524.96
#Sta/Elev= 30
  4707.2 1534.93  4728.3 1534.38  4759.9 1531.91  4819.5 1529.97  4833.7 1530.18
  4854.8 1528.43  4865.3 1528.09  4896.9 1524.49  4907.5 1522.47    4918 1522.88
  4928.5 1524.98  4939.1 1525.26  4949.6 1524.62  4981.1 1524.42  4991.5 1522.72
  4999.8  1522.4  5000.1  1521.9  5003.6  1521.9  5003.8  1522.4  5009.8 1523.16
    5015 1522.55  5032.8 1525.66  5038.4 1526.02  5168.4 1531.01  5190.7 1532.27
  5204.7 1534.23  5227.1 1535.09  5261.8 1537.97  5294.1 1540.42  5338.9 1542.83
#Mann= 5 ,-1 , 0
  4707.2    .035       0  4819.5     .07       0  4999.8     .05       0
  5003.8     .07       0  5261.8    .035       0
Bank Sta=4999.8,5003.8
XS Rating Curve= 0 ,0
Exp/Cntr=0.3,0.1

Type RM Length L Ch R = 1 ,3652    ,450,450,450
BEGIN DESCRIPTION:
Stream0176 8.0
END DESCRIPTION:
XS GIS Cut Line= 3
      1984624.96     13884074.98        1984875.       13884175.
      1985025.01     13884275.01
#Sta/Elev= 30
  4730.2 1524.81  4762.6 1523.68  4798.9 1520.65  4823.1 1517.25  4924.1 1515.05
    4946 1514.06  4960.5 1513.79    4978 1511.46  4988.1 1510.94  4988.3 1510.44
  4991.8 1510.44  4992.1 1510.94  4996.8 1512.73    5013 1512.71    5022 1513.53
  5028.1 1513.01  5049.1 1513.14  5058.1 1513.97  5064.1 1513.33  5071.6 1514.46
  5079.1 1516.97  5085.1 1517.38  5094.2 1520.09  5100.2  1520.6  5107.7 1522.96
  5136.2 1524.87  5143.7 1525.62  5152.4 1527.38  5166.3 1528.86  5179.8 1529.18
#Mann= 5 ,-1 , 0
  4730.2     .07       0    4946      .1       0  4988.1     .05       0
  4992.1      .1       0  5152.4    .035       0
Bank Sta=4988.1,4992.1
XS Rating Curve= 0 ,0
Exp/Cntr=0.3,0.1

Type RM Length L Ch R = 1 ,3202    ,172,172,172
BEGIN DESCRIPTION:
Stream0176 7.0
END DESCRIPTION:
XS GIS Cut Line= 3
      1984524.98     13884224.96        1984675.       13884525.
      1984775.04     13884575.02
#Sta/Elev= 30
  4664.6  1521.5    4701 1520.04  4740.1 1516.91  4745.7 1517.07  4762.5 1515.67
  4768.1 1515.57  4784.8 1513.79  4790.4 1513.58  4829.6 1509.24  4843.5 1508.82
  4865.9  1506.4  4879.9 1505.46  4932.6 1503.98  4946.9 1504.25  4963.7 1503.43
  4969.3 1504.02  4991.7 1503.83  5002.8 1503.32  5006.4 1502.74  5006.7 1502.24
  5010.2 1502.24  5010.4 1502.74    5014 1503.91  5022.4 1504.87  5030.8 1507.05
  5044.8 1511.87  5053.2 1513.06  5075.5 1513.53  5103.5 1514.78  5111.9  1515.5
#Mann= 4 ,-1 , 0
  4664.6     .07       0  4932.6      .1       0  5006.4     .05       0
  5010.4      .1       0
Bank Sta=5006.4,5010.4
XS Rating Curve= 0 ,0
Exp/Cntr=0.3,0.1

Type RM Length L Ch R = 1 ,3030    ,241,241,241
BEGIN DESCRIPTION:
Mapping XS 16c6350b
END DESCRIPTION:
XS GIS Cut Line= 2
      1984066.76     13884717.87       1984944.3     13884638.79
#Sta/Elev= 30
  4401.6 1519.73  4409.9 1518.56    4430 1519.19    4450  1517.2  4479.5 1516.61
  4500.2 1516.58  4550.4 1514.01  4564.6 1510.99  4598.1 1502.44  4620.7 1499.63
  4670.9 1496.95  4759.3  1495.5  4759.5    1495  4763.3  1495.5  4851.7 1498.06
    4931 1497.84  4972.1 1499.15  4982.2 1497.55  4992.2 1498.58  5032.4 1507.32
  5041.9 1509.65  5046.9 1512.18  5091.8 1514.43  5152.8 1516.47    5183 1518.61
    5193 1520.71  5203.1 1521.59  5263.3 1522.74  5279.1 1524.08  5282.7 1524.19
#Mann= 7 ,-1 , 0
  4401.6     .07       0  4479.5    .035       0  4564.6     .07       0
  4759.3     .05       0  4763.3     .07       0  5091.8      .1       0
  5279.1     .07       0
Bank Sta=4759.3,4763.3
XS Rating Curve= 0 ,0
Exp/Cntr=0.3,0.1

Type RM Length L Ch R = 1 ,2789    ,257,257,257
BEGIN DESCRIPTION:
Stream0176 6.0
END DESCRIPTION:
XS GIS Cut Line= 3
      1984141.17     13884994.61        1984675.       13884875.
      1984824.97     13884775.02
#Sta/Elev= 30
  4453.4    1525  4467.6 1524.34  4478.7 1522.64  4528.2 1520.24  4565.4 1517.93
  4608.8  1517.2  4631.5 1515.66    4652 1511.47  4657.3 1508.81  4672.8 1505.29
  4705.8 1499.43  4717.3 1498.89    4744 1498.24  4792.5 1491.26    4814 1489.68
  4814.2 1489.18    4818 1489.68  4826.2 1490.84  4832.1  1490.6  4877.5  1490.1
  4918.5 1491.52    5008 1491.25    5044 1492.33  5065.1 1494.18  5086.1 1493.54
  5101.1 1496.26  5131.2 1504.14  5158.2 1513.48  5164.2  1513.8  5180.7 1514.78
#Mann= 8 ,-1 , 0
  4453.4     .07       0  4528.2    .035       0  4672.8     .07       0
  4717.3     .07       0    4814     .05       0    4818     .07       0
  4832.1     .07       0  5164.2      .1       0
Bank Sta=4814,4818
XS Rating Curve= 0 ,0
Exp/Cntr=0.3,0.1

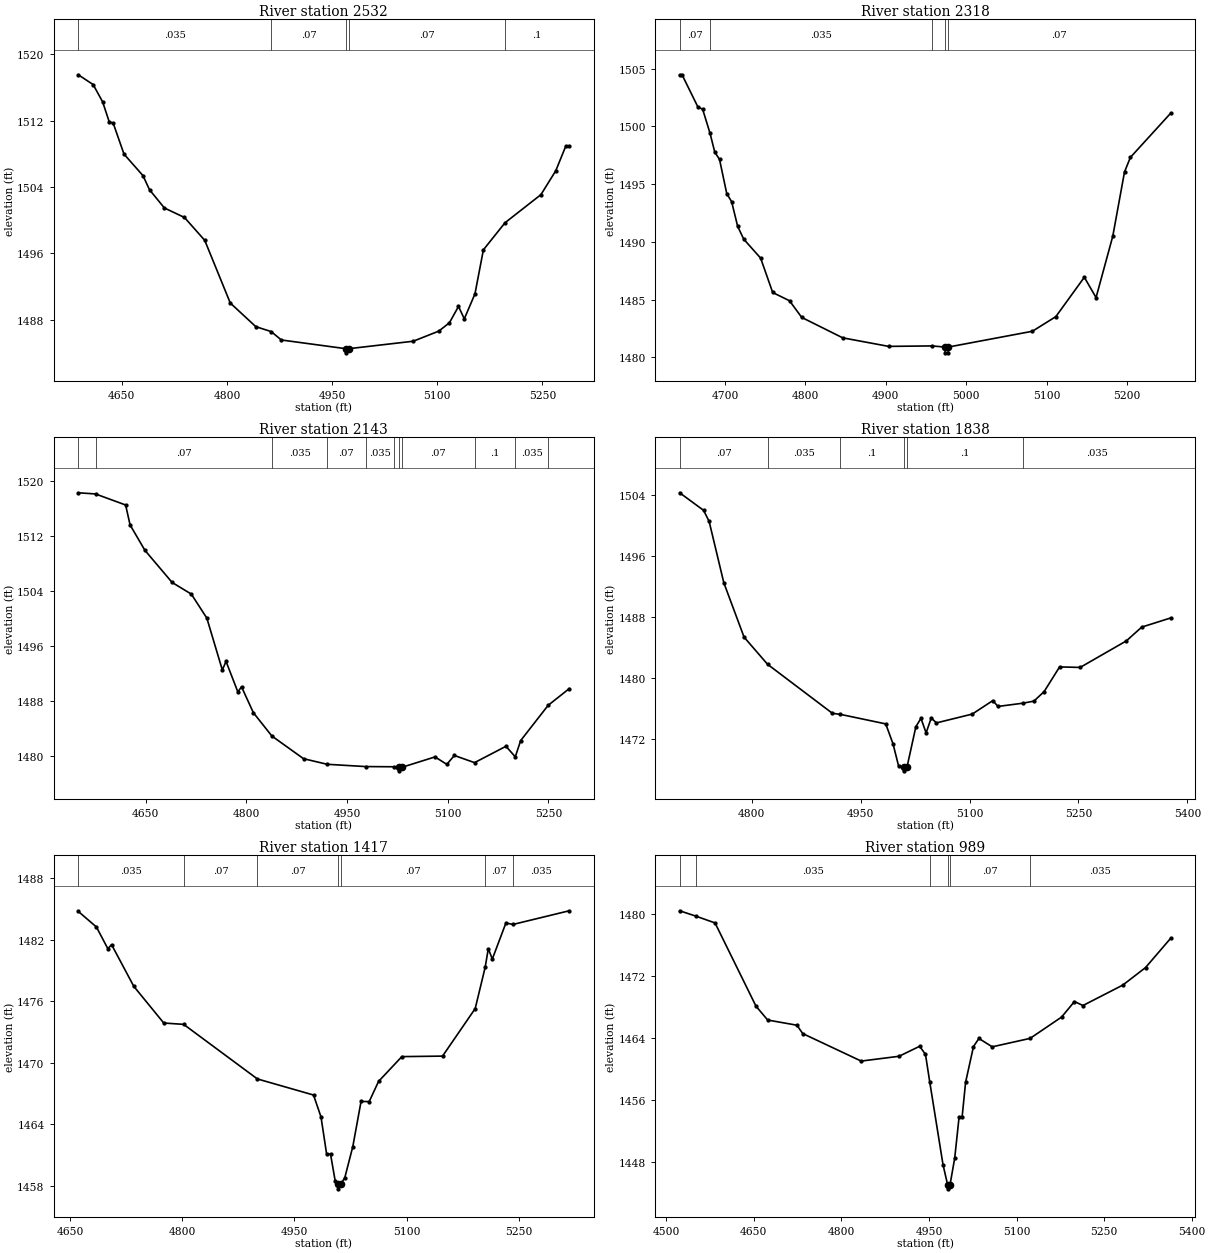
Type RM Length L Ch R = 1 ,2532    ,214,214,214
BEGIN DESCRIPTION:
Mapping XS 3e502dfc
END DESCRIPTION:
XS GIS Cut Line= 2
      1984407.11     13885326.27      1984998.33     13884951.11
#Sta/Elev= 30
  4587.9 1517.54  4609.1 1516.36  4622.6 1514.28  4631.9  1511.9  4637.8 1511.68
  4653.1 1507.97  4680.2 1505.37  4689.5 1503.67  4710.7 1501.47  4739.4 1500.32
  4768.3 1497.56  4804.7    1490  4841.1 1487.15  4862.9 1486.56  4877.6 1485.54
  4969.6 1484.49  4969.8 1483.99  4973.6 1484.49  5065.6 1485.39  5102.1 1486.61
  5117.3 1487.62  5130.2 1489.59  5138.5 1488.09  5153.7 1491.11  5165.7 1496.42
  5196.6 1499.69  5247.8 1503.08    5269 1505.97  5283.2 1508.93  5288.1 1508.93
#Mann= 5 ,-1 , 0
  4587.9    .035       0  4862.9     .07       0  4969.6     .05       0
  4973.6     .07       0  5196.6      .1       0
Bank Sta=4969.6,4973.6
XS Rating Curve= 0 ,0
Exp/Cntr=0.3,0.1

Type RM Length L Ch R = 1 ,2318    ,175,175,175
BEGIN DESCRIPTION:
Stream0176 5.0
END DESCRIPTION:
XS GIS Cut Line= 3
      1984574.97     13885475.02        1984875.       13885275.
      1985025.01     13885074.99
#Sta/Elev= 30
  4643.6 1504.48  4646.6 1504.48  4666.2  1501.7  4672.2 1501.49  4681.3 1499.43
  4687.2 1497.79  4693.2 1497.14  4702.2 1494.17  4708.2 1493.49  4715.7 1491.35
  4723.3 1490.23  4744.3 1488.59  4759.3 1485.61  4780.3 1484.89  4795.4 1483.45
  4846.4 1481.68  4903.5 1480.94  4957.3 1480.98  4973.6 1480.88  4973.9 1480.38
  4977.4 1480.38  4977.6 1480.88  5082.3 1482.25  5111.5 1483.52  5146.9 1486.93
  5161.5 1485.17  5182.3 1490.49  5196.9 1496.06  5204.2 1497.32  5254.2 1501.14
#Mann= 5 ,-1 , 0
  4643.6     .07       0  4681.3    .035       0  4957.3     .07       0
  4973.6     .05       0  4977.6     .07       0
Bank Sta=4973.6,4977.6
XS Rating Curve= 0 ,0
Exp/Cntr=0.3,0.1

Type RM Length L Ch R = 1 ,2143    ,305,305,305
BEGIN DESCRIPTION:
Mapping XS 2b4674e7
END DESCRIPTION:
XS GIS Cut Line= 2
      1984464.63     13885638.58      1985130.86     13885337.01
#Sta/Elev= 30
  4549.6 1518.22  4575.3 1518.05  4620.1 1516.45  4626.8 1513.55  4648.8 1509.88
  4689.4 1505.21    4718 1503.52  4741.1 1500.04  4764.2 1492.51  4769.7 1493.76
  4787.3 1489.33  4792.8 1490.07  4810.4 1486.32    4838 1482.93  4885.2 1479.64
  4920.4 1478.83  4977.5  1478.5  5019.8 1478.47  5027.3 1478.38  5027.6 1477.88
  5031.3 1478.38    5081  1479.9  5098.6 1478.82  5109.8 1480.11  5139.9 1479.07
  5186.7 1481.44  5200.6 1479.91  5208.6 1482.27  5249.6 1487.39  5280.9  1489.8
#Mann= 11 ,-1 , 0
  4549.6    .035       0  4575.3     .07       0    4838    .035       0
  4920.4     .07       0  4977.5    .035       0  5019.8     .07       0
  5027.3     .05       0  5031.3     .07       0  5139.9      .1       0
  5200.6    .035       0  5249.6      .1       0
Bank Sta=5027.3,5031.3
XS Rating Curve= 0 ,0
Exp/Cntr=0.3,0.1

Type RM Length L Ch R = 1 ,1838    ,421,421,421
BEGIN DESCRIPTION:
Stream0176 4.0
END DESCRIPTION:
XS GIS Cut Line= 3
      1984674.98       13885775.        1984975.       13885725.
      1985238.96     13885462.67
#Sta/Elev= 30
  4700.6 1504.33  4733.6 1502.02  4741.2 1500.57  4761.4 1492.53  4789.3 1485.39
  4821.7 1481.82    4911 1475.39  4922.1 1475.25  4984.5    1474  4994.6 1471.36
  5002.2 1468.47  5009.8 1468.34  5010.1 1467.84  5013.8 1468.34    5026 1473.63
    5033 1474.73  5040.1 1472.82  5047.2 1474.78  5054.3 1474.13  5103.7 1475.29
    5132 1477.06  5139.1 1476.29  5173.7 1476.72  5188.6 1476.99  5202.7 1478.24
    5224 1481.48  5252.3 1481.41  5315.9 1484.89  5337.1  1486.7  5376.9  1487.9
#Mann= 6 ,-1 , 0
  4700.6     .07       0  4821.7    .035       0  4922.1      .1       0
  5009.8     .05       0  5013.8      .1       0  5173.7    .035       0
Bank Sta=5009.8,5013.8
XS Rating Curve= 0 ,0
Exp/Cntr=0.3,0.1

Type RM Length L Ch R = 1 ,1417    ,428,428,428
BEGIN DESCRIPTION:
Stream0176 3.0
END DESCRIPTION:
XS GIS Cut Line= 3
      1984840.79     13886069.32        1985175.       13886075.
      1985470.34     13885947.62
#Sta/Elev= 30
  4661.2 1484.77  4685.4 1483.25  4700.7 1481.13  4705.7 1481.52  4735.4 1477.45
  4775.4 1473.87    4802 1473.74  4900.5 1468.41  4975.5 1466.84  4985.5  1464.7
    4993 1461.08  4998.2 1461.08  5004.5 1458.43  5007.9 1458.18  5008.2 1457.68
  5011.9 1458.18  5017.2 1458.74    5028 1461.81    5039 1466.21  5049.9  1466.2
  5062.4 1468.17  5093.5 1470.59  5147.9 1470.64  5191.5 1475.28  5204.8  1479.3
    5209 1481.12  5214.4 1480.12  5232.5 1483.63  5242.2  1483.5  5317.1 1484.83
#Mann= 7 ,-1 , 0
  4661.2    .035       0    4802     .07       0  4900.5     .07       0
  5007.9     .05       0  5011.9     .07       0  5204.8     .07       0
  5242.2    .035       0
Bank Sta=5007.9,5011.9
XS Rating Curve= 0 ,0
Exp/Cntr=0.3,0.1

Type RM Length L Ch R = 1 ,989     ,472,472,472
BEGIN DESCRIPTION:
Stream0176 2.0
END DESCRIPTION:
XS GIS Cut Line= 4
      1984844.47     13886402.21        1985325.       13886425.
      1985450.54     13886366.05       1985545.1     13886166.26
#Sta/Elev= 30
    4523 1480.39  4551.1 1479.69  4583.6 1478.82  4653.7 1468.08  4673.7 1466.29
  4723.8 1465.62  4733.8 1464.54  4833.9 1460.99  4898.7 1461.61    4934  1462.9
    4944 1461.86  4951.3  1458.3    4974 1447.63    4982    1445  4982.3  1444.5
    4986    1445  4994.1 1448.48  5001.6  1453.8  5006.8  1453.8  5012.7 1458.25
  5026.2 1462.86  5035.5 1463.91  5058.3 1462.83  5123.2 1463.92  5177.1 1466.67
  5199.2 1468.68  5213.7 1468.16    5282  1470.8  5320.9 1473.06  5363.8 1476.83
#Mann= 6 ,-1 , 0
    4523     .07       0  4551.1    .035       0  4951.3     .07       0
    4982     .05       0    4986     .07       0  5123.2    .035       0
Bank Sta=4982,4986
XS Rating Curve= 0 ,0
Exp/Cntr=0.3,0.1

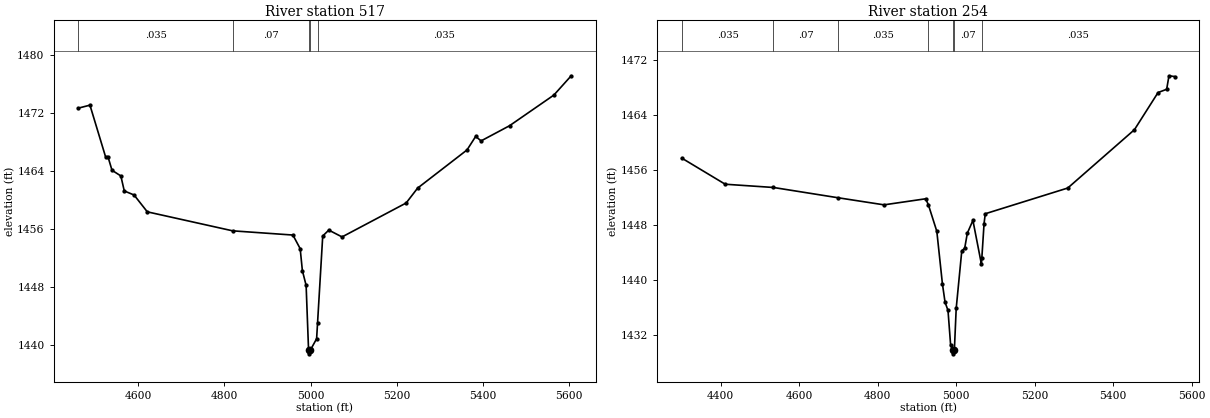
Type RM Length L Ch R = 1 ,517     ,263,263,263
BEGIN DESCRIPTION:
Stream0176 1.0
END DESCRIPTION:
XS GIS Cut Line= 4
      1984948.74      13886894.2        1985475.       13886775.
        1985525.       13886725.      1985599.57     13886195.12
#Sta/Elev= 30
  4460.4 1472.67  4487.3 1473.08  4523.9  1465.9  4529.1 1465.98  4538.6  1464.1
  4559.1 1463.32  4567.1 1461.25  4589.9 1460.69  4620.6 1458.37    4819 1455.75
    4959 1455.17  4975.9 1453.29    4981 1450.27  4989.7 1448.23  4995.4 1439.29
  4995.7 1438.79  4999.4 1439.29  5014.1 1440.87  5016.3 1443.07  5028.3 1455.04
  5042.4 1455.85  5073.2 1454.91  5222.2 1459.59  5248.8 1461.64  5363.6  1466.9
  5383.8 1468.77  5396.3 1468.15  5462.4 1470.24  5565.5 1474.47  5605.8 1477.13
#Mann= 5 ,-1 , 0
  4460.4    .035       0    4819     .07       0  4995.4     .05       0
  4999.4     .07       0  5016.3    .035       0
Bank Sta=4995.4,4999.4
XS Rating Curve= 0 ,0
Exp/Cntr=0.3,0.1

Type RM Length L Ch R = 1 ,254     ,0,0,0
BEGIN DESCRIPTION:
Stream0176 0.0
END DESCRIPTION:
XS GIS Cut Line= 4
      1985054.27     13887062.98      1985532.87     13887044.43
      1985752.23     13886847.82      1985979.61     13886422.41
#Sta/Elev= 30
  4300.6 1457.71  4411.4 1453.92  4534.2 1453.45  4699.9 1451.95  4816.1 1450.93
  4922.2 1451.81  4929.1 1450.94  4950.6 1447.09  4964.9 1439.46  4971.6  1436.8
  4979.1 1435.62  4985.8 1430.58  4991.3 1429.82  4991.5 1429.32  4995.3 1429.82
    5000 1435.91  5014.2 1444.25  5021.7 1444.66  5028.4 1446.83  5042.6 1448.67
  5064.3 1442.32  5065.3  1443.2    5071 1448.22  5074.1 1449.64  5284.3 1453.37
  5454.2 1461.83  5514.4 1467.22  5536.3 1467.69  5542.2 1469.65  5556.5 1469.54
#Mann= 7 ,-1 , 0
  4300.6    .035       0  4534.2     .07       0  4699.9    .035       0
  4929.1     .07       0  4991.3     .05       0  4995.3     .07       0
  5065.3    .035       0
Bank Sta=4991.3,4995.3
XS Rating Curve= 0 ,0
Exp/Cntr=0.3,0.1

Chan Stop Cuts=-1
Use User Specified Reach Order=0
Composite Channel Slope=5