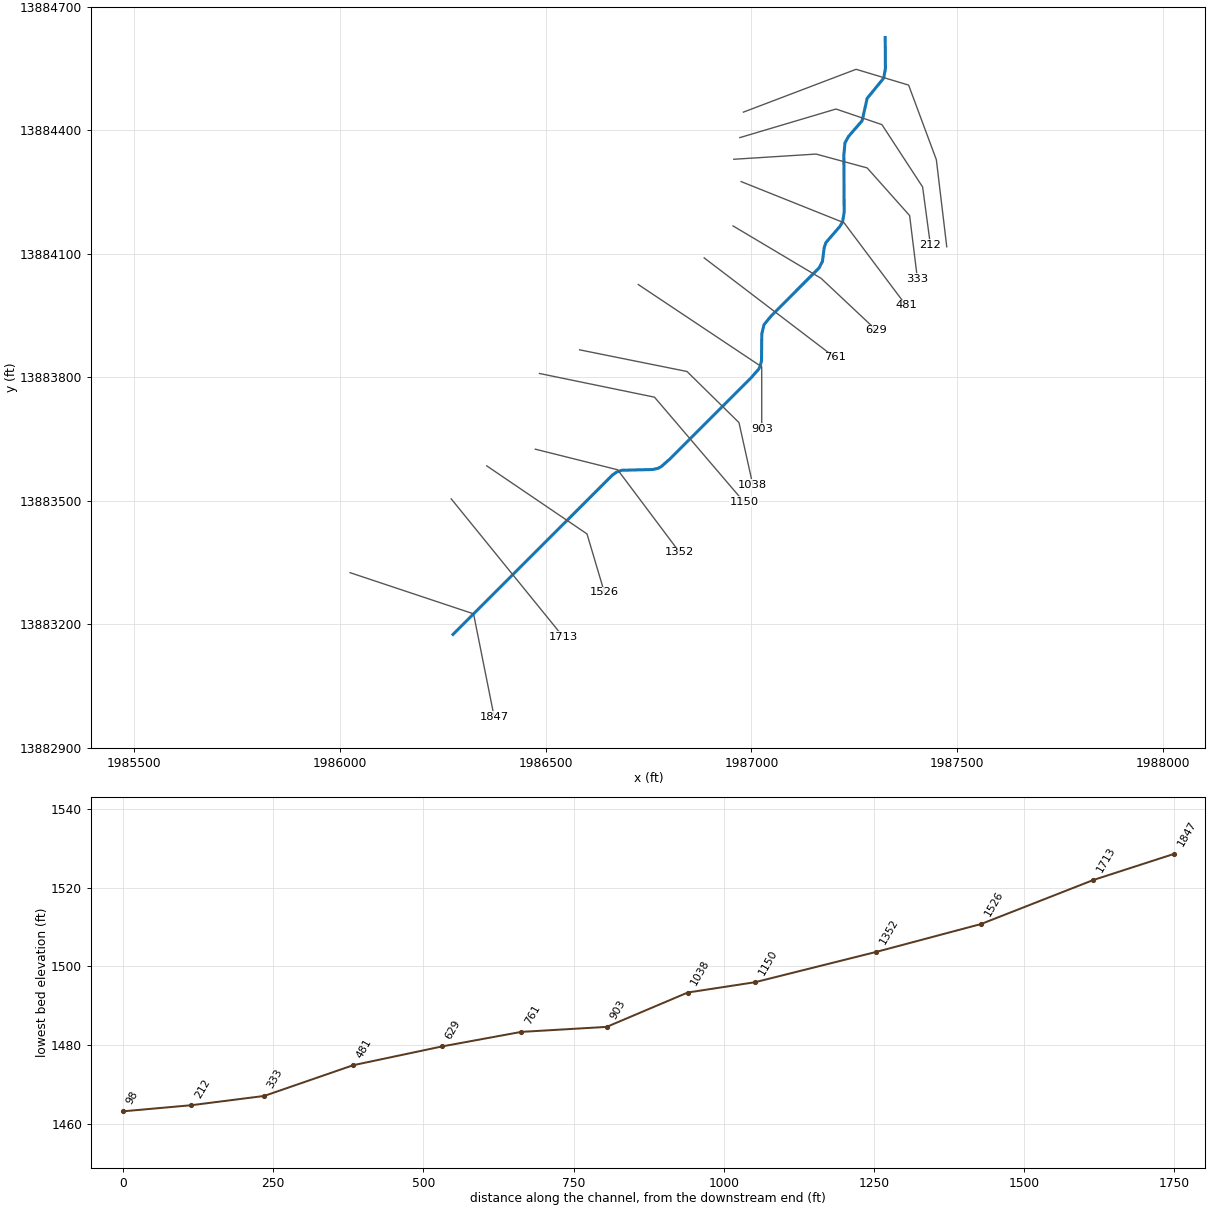
--- Stream0179.prj (project) ---

Proj Title=Stream0179 Base Level Engineering
Current Plan=p01
Default Exp/Contr=0.3,0.1
English Units
Geom File=g01
Flow File=f01
Plan File=p01
Y Axis Title=Elevation
X Axis Title(PF)=Main Channel Distance
X Axis Title(XS)=Station
BEGIN DESCRIPTION:
Stream0179
END DESCRIPTION:
DSS Export Rating Curves= 0
DSS Export Rating Curve Sorted= 0
DSS Export Volume Flow Curves= 0
DXF OffsetX= 0
DXF OffsetY= 0
DXF ScaleX= 1
DXF ScaleY= 10

--- Stream0179.p01 (plan) ---

Plan Title=Multiple Run
Short Identifier=Multiple
Geom File=g01
Flow File=f01
Subcritical Flow
K Sum by GR= 0
Std Step Tol= 0.01
Critical Tol= 0.01
Num of Std Step Trials= 20
Max Error Tol= 0.3
Flow Tol Ratio= 0.001
Split Flow NTrial= 30
Split Flow Tol= 0.02
Split Flow Ratio= 0.02
Log Output Level= 0
Friction Slope Method= 1
Unsteady Friction Slope Method= 2
Unsteady Bridges Friction Slope Method= 1
Parabolic Critical Depth
Global Vel Dist=  1 , 1 , 1
Global Log Level= 0
CheckData=True
Encroach Param= -1, 0, 0, 0
BEGIN DESCRIPTION:
Multiple Run
END DESCRIPTION:

--- Stream0179.f01 (steady flow) ---

Flow Title=Multiple
Number of Profiles=7
Profile Names=10-year,25-year,50-year,1pct_min,100-year,1pct_plu,500-year
River Rch & RM= Stream0179,Reach-1,1847
     212     324     420     267     532    1062     838
Boundary for River Rch & Prof#=Stream0179,Reach-1,1
Up Type=0
Dn Type=3
Dn Slope=0.005
Boundary for River Rch & Prof#=Stream0179,Reach-1,2
Up Type=0
Dn Type=3
Dn Slope=0.005
Boundary for River Rch & Prof#=Stream0179,Reach-1,3
Up Type=0
Dn Type=3
Dn Slope=0.005
Boundary for River Rch & Prof#=Stream0179,Reach-1,4
Up Type=0
Dn Type=3
Dn Slope=0.005
Boundary for River Rch & Prof#=Stream0179,Reach-1,5
Up Type=0
Dn Type=3
Dn Slope=0.005
Boundary for River Rch & Prof#=Stream0179,Reach-1,6
Up Type=0
Dn Type=3
Dn Slope=0.005
Boundary for River Rch & Prof#=Stream0179,Reach-1,7
Up Type=0
Dn Type=3
Dn Slope=0.005

--- Stream0179.g01 (geometry) ---

Geom Title=Existing Conditions

River Reach=Stream0179,Reach-1
Reach XY= 30
      1986275.00     13883175.00      1986661.70     13883561.60
      1986672.57     13883569.48      1986685.48     13883573.83
      1986759.78     13883575.53      1986773.50     13883578.61
      1986781.17     13883582.86      1986801.87     13883601.18
      1986998.82     13883798.13      1987017.14     13883818.83
      1987021.39     13883826.50      1987024.47     13883840.22
      1987025.13     13883904.94      1987030.52     13883927.43
      1987047.88     13883948.52      1987164.24     13884065.32
      1987172.50     13884081.03      1987176.72     13884114.29
      1987181.14     13884127.17      1987214.21     13884165.33
      1987221.25     13884176.55      1987225.21     13884199.91
      1987224.57     13884340.18      1987227.24     13884369.07
      1987235.80     13884384.67      1987268.88     13884422.82
      1987281.09     13884477.19      1987321.37     13884526.50
      1987325.48     13884549.80      1987325.00     13884625.00

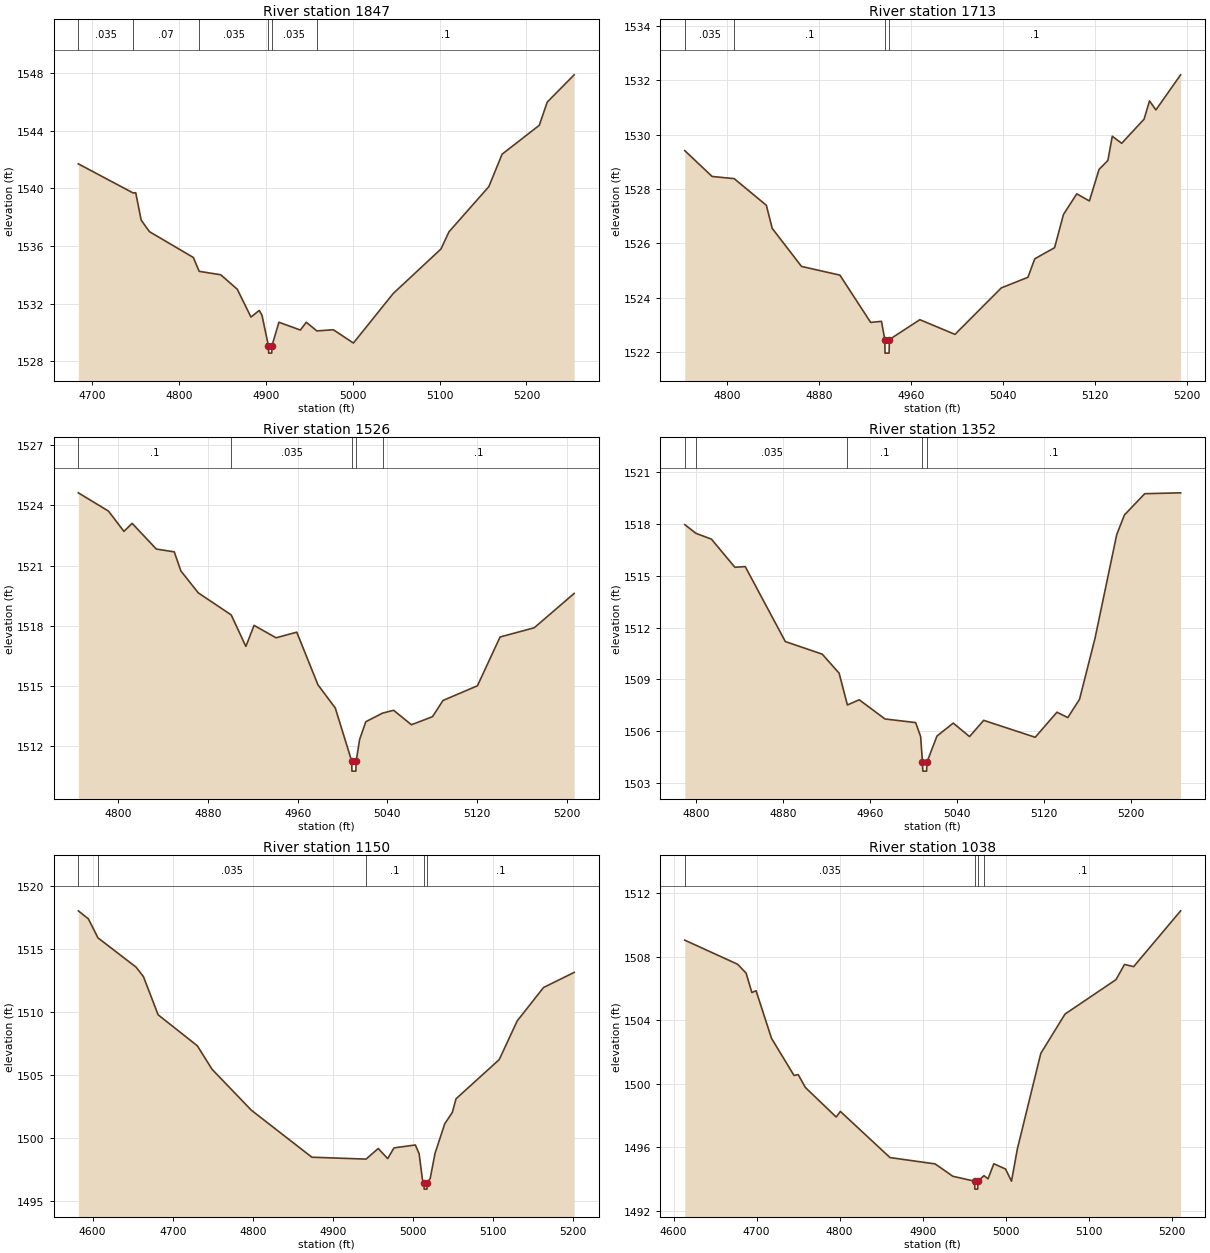
Type RM Length L Ch R = 1,1847,134,134,134
BEGIN DESCRIPTION:
Stream0179 4.0
END DESCRIPTION:
XS GIS Cut Line= 3
      1986025.02     13883324.99      1986325.00     13883225.00
      1986375.01     13882974.96
#Sta/Elev= 30
  4683.8 1541.70  4747.0 1539.68  4749.9 1539.70  4756.2 1537.80  4765.7 1537.00
  4816.3 1535.21  4823.0 1534.25  4847.9 1534.01  4866.9 1533.01  4882.7 1531.08
  4892.2 1531.54  4895.4 1531.20  4902.8 1529.08  4903.1 1528.58  4906.6 1528.58
  4906.8 1529.08  4914.9 1530.72  4939.6 1530.18  4946.4 1530.72  4958.6 1530.12
  4977.6 1530.20  5000.7 1529.28  5046.5 1532.71  5101.6 1535.80  5110.8 1536.99
  5156.7 1540.12  5172.0 1542.37  5214.8 1544.37  5224.0 1545.98  5255.0 1547.87
#Mann=6,-1,0
  4683.8   0.035       0  4747.0    0.07       0  4823.0   0.035       0
  4902.8    0.05       0  4906.8   0.035       0  4958.6     0.1       0
Bank Sta=4902.8,4906.8
Exp/Cntr=0.3,0.1

Type RM Length L Ch R = 1,1713,187,187,187
BEGIN DESCRIPTION:
Mapping XS 97336f42
END DESCRIPTION:
XS GIS Cut Line= 2
      1986270.74     13883504.27      1986542.78     13883169.20
#Sta/Elev= 30
  4762.9 1529.41  4786.7 1528.46  4805.9 1528.38  4833.9 1527.40  4839.0 1526.55
  4864.5 1525.15  4897.9 1524.83  4924.7 1523.09  4934.1 1523.13  4937.0 1522.46
  4937.2 1521.96  4940.7 1521.96  4941.0 1522.46  4967.5 1523.19  4998.1 1522.65
  5038.4 1524.36  5061.6 1524.75  5067.5 1525.43  5084.8 1525.84  5092.5 1527.06
  5104.1 1527.82  5115.1 1527.56  5123.5 1528.72  5131.2 1529.05  5135.0 1529.94
  5143.2 1529.68  5162.7 1530.57  5167.4 1531.24  5173.0 1530.91  5194.5 1532.20
#Mann=4,-1,0
  4762.9   0.035       0  4805.9     0.1       0  4937.0    0.05       0
  4941.0     0.1       0
Bank Sta=4937,4941
Exp/Cntr=0.3,0.1

Type RM Length L Ch R = 1,1526,174,174,174
BEGIN DESCRIPTION:
Mapping XS 5ecd920c
END DESCRIPTION:
XS GIS Cut Line= 3
      1986357.03     13883584.44      1986600.53     13883419.15
      1986642.80     13883277.21
#Sta/Elev= 30
  4764.3 1524.62  4791.2 1523.71  4805.0 1522.70  4812.3 1523.10  4833.9 1521.82
  4849.9 1521.68  4855.8 1520.73  4871.3 1519.64  4900.7 1518.54  4913.8 1516.97
  4921.1 1518.02  4940.7 1517.40  4959.2 1517.68  4978.1 1515.06  4993.6 1513.90
  5008.2 1511.26  5008.4 1510.76  5011.9 1510.76  5012.2 1511.26  5015.3 1512.34
  5020.8 1513.22  5035.8 1513.65  5045.6 1513.79  5061.5 1513.07  5080.3 1513.47
  5089.7 1514.28  5120.4 1515.01  5140.6 1517.44  5171.1 1517.90  5206.7 1519.61
#Mann=5,-1,0
  4764.3     0.1       0  4900.7   0.035       0  5008.2   0.035       0
  5012.2   0.035       0  5035.8     0.1       0
Bank Sta=5008.2,5012.2
Exp/Cntr=0.3,0.1

Type RM Length L Ch R = 1,1352,202,202,202
BEGIN DESCRIPTION:
Stream0179 3.0
END DESCRIPTION:
XS GIS Cut Line= 3
      1986474.97     13883625.01      1986675.00     13883575.00
      1986825.01     13883374.99
#Sta/Elev= 30
  4789.7 1517.96  4800.1 1517.45  4814.2 1517.12  4835.8 1515.49  4845.3 1515.53
  4882.2 1511.19  4916.2 1510.46  4931.7 1509.36  4939.3 1507.52  4950.2 1507.82
  4973.9 1506.71  5002.1 1506.50  5006.7 1505.69  5008.4 1504.19  5008.7 1503.69
  5012.2 1503.69  5012.4 1504.19  5021.7 1505.72  5036.7 1506.47  5051.7 1505.69
  5064.7 1506.63  5112.1 1505.65  5132.1 1507.10  5142.1 1506.79  5152.9 1507.85
  5167.1 1511.37  5187.1 1517.38  5194.2 1518.52  5212.9 1519.75  5245.9 1519.80
#Mann=5,-1,0
  4789.7     0.1       0  4800.1   0.035       0  4939.3     0.1       0
  5008.4    0.05       0  5012.4     0.1       0
Bank Sta=5008.4,5012.4
Exp/Cntr=0.3,0.1

Type RM Length L Ch R = 1,1150,112,112,112
BEGIN DESCRIPTION:
Mapping XS 2de8a870
END DESCRIPTION:
XS GIS Cut Line= 3
      1986485.07     13883808.90      1986764.47     13883751.36
      1986981.56     13883497.23
#Sta/Elev= 30
  4582.1 1518.03  4594.7 1517.39  4606.6 1515.89  4654.2 1513.57  4663.4 1512.82
  4681.8 1509.79  4730.8 1507.33  4749.2 1505.47  4798.2 1502.23  4873.9 1498.50
  4941.6 1498.35  4956.8 1499.19  4968.6 1498.39  4976.5 1499.24  5003.2 1499.47
  5007.9 1498.78  5012.0 1496.74  5014.0 1496.47  5014.2 1495.97  5017.7 1495.97
  5018.0 1496.47  5021.7 1496.81  5027.8 1498.81  5039.9 1501.15  5049.4 1502.05
  5054.0 1503.13  5108.0 1506.24  5130.4 1509.30  5163.3 1511.95  5201.6 1513.15
#Mann=5,-1,0
  4582.1     0.1       0  4606.6   0.035       0  4941.6     0.1       0
  5014.0    0.05       0  5018.0     0.1       0
Bank Sta=5014,5018
Exp/Cntr=0.3,0.1

Type RM Length L Ch R = 1,1038,135,135,135
BEGIN DESCRIPTION:
Stream0179 G
END DESCRIPTION:
XS GIS Cut Line= 4
      1986582.57     13883866.33      1986843.49     13883813.73
      1986969.75     13883689.58      1987003.21     13883539.00
#Sta/Elev= 30
  4613.4 1509.05  4677.1 1507.53  4687.3 1506.97  4694.2 1505.75  4699.3 1505.86
  4717.9 1502.86  4745.0 1500.52  4750.1 1500.57  4758.7 1499.76  4795.8 1497.90
  4800.9 1498.25  4860.7 1495.34  4915.1 1494.94  4936.4 1494.16  4962.6 1493.85
  4962.9 1493.35  4966.4 1493.35  4966.6 1493.85  4974.0 1494.20  4978.8 1494.00
  4985.8 1494.95  4999.9 1494.62  5007.1 1493.85  5014.1 1495.87  5042.4 1501.91
  5071.6 1504.39  5133.0 1506.56  5143.3 1507.52  5154.3 1507.38  5210.9 1510.90
#Mann=4,-1,0
  4613.4   0.035       0  4962.6    0.05       0  4966.6   0.035       0
  4974.0     0.1       0
Bank Sta=4962.6,4966.6
Exp/Cntr=0.3,0.1

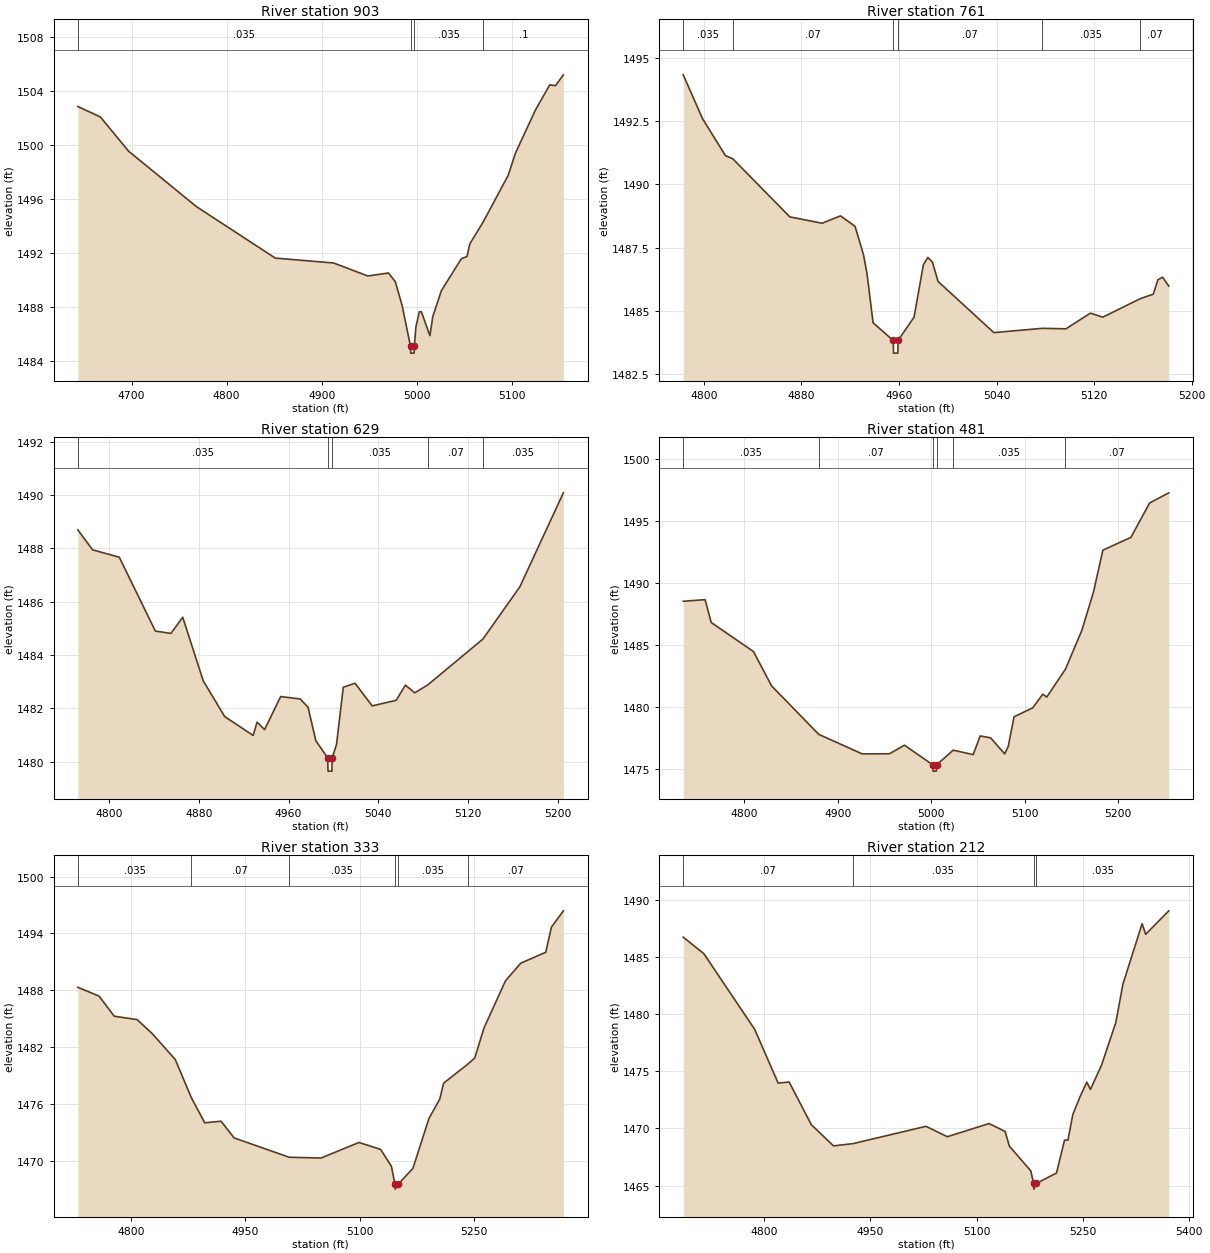
Type RM Length L Ch R = 1,903,142,142,142
BEGIN DESCRIPTION:
Stream0179 2.0
END DESCRIPTION:
XS GIS Cut Line= 3
      1986725.01     13884024.99      1987025.00     13883825.00
      1987025.00     13883675.05
#Sta/Elev= 30
  4643.5 1502.83  4667.2 1502.06  4696.9 1499.53  4768.1 1495.44  4851.1 1491.63
  4912.4 1491.27  4948.4 1490.31  4970.1 1490.53  4977.3 1489.89  4984.5 1488.12
  4993.3 1485.11  4993.5 1484.61  4997.0 1484.61  4997.3 1485.11  4998.9 1486.52
  5002.5 1487.66  5004.7 1487.67  5013.7 1485.90  5016.7 1487.31  5025.7 1489.22
  5046.7 1491.58  5052.7 1491.75  5055.7 1492.69  5069.7 1494.30  5096.0 1497.75
  5103.7 1499.40  5124.7 1502.58  5139.7 1504.43  5145.7 1504.37  5154.0 1505.17
#Mann=4,-1,0
  4643.5   0.035       0  4993.3   0.035       0  4997.3   0.035       0
  5069.7     0.1       0
Bank Sta=4993.3,4997.3
Exp/Cntr=0.3,0.1

Type RM Length L Ch R = 1,761,132,132,132
BEGIN DESCRIPTION:
Mapping XS cf074196
END DESCRIPTION:
XS GIS Cut Line= 2
      1986885.19     13884089.66      1987201.79     13883848.48
#Sta/Elev= 30
  4783.2 1494.33  4799.0 1492.60  4817.8 1491.14  4823.7 1491.02  4870.6 1488.72
  4897.0 1488.47  4912.1 1488.76  4924.0 1488.35  4931.0 1487.22  4933.9 1486.46
  4938.8 1484.54  4955.3 1483.84  4955.6 1483.34  4959.1 1483.34  4959.3 1483.84
  4972.4 1484.76  4980.0 1486.82  4983.7 1487.12  4987.5 1486.93  4992.1 1486.17
  5037.8 1484.15  5077.6 1484.32  5096.9 1484.30  5117.0 1484.92  5127.1 1484.76
  5157.8 1485.49  5168.5 1485.67  5172.3 1486.24  5176.1 1486.34  5181.2 1485.99
#Mann=6,-1,0
  4783.2   0.035       0  4823.7    0.07       0  4955.3    0.05       0
  4959.3    0.07       0  5077.6   0.035       0  5157.8    0.07       0
Bank Sta=4955.3,4959.3
Exp/Cntr=0.3,0.1

Type RM Length L Ch R = 1,629,148,148,148
BEGIN DESCRIPTION:
Mapping XS 093fbc15
END DESCRIPTION:
XS GIS Cut Line= 3
      1986955.38     13884167.31      1987169.19     13884040.04
      1987303.29     13883914.09
#Sta/Elev= 30
  4772.1 1488.70  4785.3 1487.95  4809.1 1487.67  4841.2 1484.90  4855.1 1484.81
  4865.6 1485.42  4883.9 1483.03  4903.0 1481.69  4928.4 1480.98  4931.9 1481.48
  4938.6 1481.20  4952.9 1482.44  4970.3 1482.35  4977.3 1482.04  4984.3 1480.78
  4994.8 1480.14  4995.1 1479.64  4998.6 1479.64  4998.8 1480.14  5002.7 1480.64
  5008.7 1482.79  5019.2 1482.94  5034.5 1482.09  5055.9 1482.30  5064.1 1482.87
  5072.4 1482.58  5084.1 1482.88  5133.2 1484.60  5166.1 1486.56  5204.9 1490.09
#Mann=5,-1,0
  4772.1   0.035       0  4994.8   0.035       0  4998.8   0.035       0
  5084.1    0.07       0  5133.2   0.035       0
Bank Sta=4994.8,4998.8
Exp/Cntr=0.3,0.1

Type RM Length L Ch R = 1,481,148,148,148
BEGIN DESCRIPTION:
Stream0179 1.0
END DESCRIPTION:
XS GIS Cut Line= 3
      1986975.00     13884275.00      1987225.00     13884175.00
      1987375.02     13883974.97
#Sta/Elev= 30
  4734.8 1488.55  4758.2 1488.68  4764.7 1486.84  4809.9 1484.50  4829.3 1481.73
  4879.8 1477.82  4926.2 1476.25  4955.3 1476.26  4971.4 1476.95  5001.8 1475.36
  5002.0 1474.86  5005.5 1474.86  5005.8 1475.36  5023.5 1476.55  5044.9 1476.19
  5052.4 1477.70  5063.6 1477.54  5078.6 1476.25  5082.4 1476.85  5088.6 1479.24
  5108.6 1479.96  5119.3 1481.06  5123.6 1480.83  5143.6 1483.08  5161.1 1486.20
  5173.6 1489.31  5183.6 1492.67  5213.6 1493.70  5233.6 1496.47  5254.1 1497.29
#Mann=6,-1,0
  4734.8   0.035       0  4879.8    0.07       0  5001.8    0.05       0
  5005.8    0.07       0  5023.5   0.035       0  5143.6    0.07       0
Bank Sta=5001.8,5005.8
Exp/Cntr=0.3,0.1

Type RM Length L Ch R = 1,333,121,121,121
BEGIN DESCRIPTION:
Stream0179 H
END DESCRIPTION:
XS GIS Cut Line= 5
      1986957.15     13884329.26      1987157.02     13884341.89
      1987281.17     13884308.22      1987384.28     13884192.49
      1987403.15     13884039.45
#Sta/Elev= 30
  4729.7 1488.33  4757.6 1487.40  4777.6 1485.28  4807.7 1484.92  4827.7 1483.43
  4857.8 1480.71  4878.7 1476.72  4896.5 1474.04  4917.9 1474.21  4935.1 1472.45
  5007.5 1470.41  5049.4 1470.33  5099.2 1471.97  5127.6 1471.24  5141.8 1469.46
  5146.5 1467.55  5146.8 1467.05  5150.5 1467.55  5170.1 1469.24  5191.1 1474.49
  5205.4 1476.55  5210.4 1478.22  5242.1 1480.22  5251.4 1480.88  5263.4 1484.02
  5291.7 1489.01  5311.8 1490.87  5344.6 1492.02  5352.1 1494.67  5367.8 1496.39
#Mann=6,-1,0
  4729.7   0.035       0  4878.7    0.07       0  5007.5   0.035       0
  5146.5    0.05       0  5150.5   0.035       0  5242.1    0.07       0
Bank Sta=5146.5,5150.5
Exp/Cntr=0.3,0.1

Type RM Length L Ch R = 1,212,114,114,114
BEGIN DESCRIPTION:
Stream0179 i
END DESCRIPTION:
XS GIS Cut Line= 5
      1986971.84     13884381.86      1987205.42     13884451.31
      1987316.94     13884413.43      1987415.84     13884261.93
      1987434.78     13884120.98
#Sta/Elev= 30
  4686.5 1486.72  4715.5 1485.28  4787.1 1478.68  4820.3 1473.97  4835.8 1474.06
  4867.1 1470.33  4898.4 1468.48  4926.2 1468.68  5028.8 1470.19  5058.8 1469.28
  5117.7 1470.43  5140.3 1469.74  5146.3 1468.46  5176.5 1466.30  5180.5 1465.20
  5180.8 1464.70  5184.5 1465.20  5212.8 1466.11  5224.1 1468.98  5228.9 1468.98
  5235.9 1471.24  5246.0 1472.78  5255.6 1474.05  5260.6 1473.41  5276.2 1475.52
  5296.4 1479.26  5306.5 1482.63  5333.5 1487.90  5338.5 1486.97  5371.1 1489.02
#Mann=4,-1,0
  4686.5    0.07       0  4926.2   0.035       0  5180.5   0.035       0
  5184.5   0.035       0
Bank Sta=5180.5,5184.5
Exp/Cntr=0.3,0.1

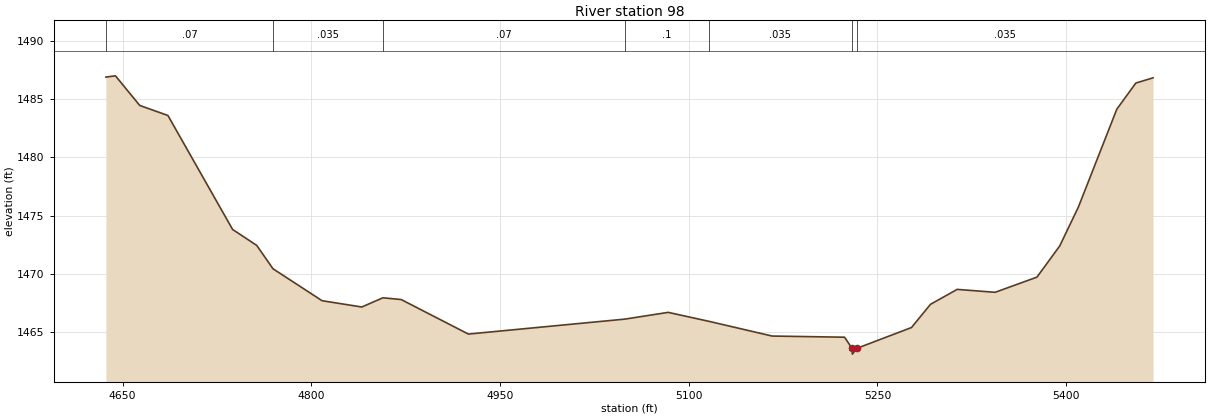
Type RM Length L Ch R = 1,98,0,0,0
BEGIN DESCRIPTION:
Stream0179 0.0
END DESCRIPTION:
XS GIS Cut Line= 5
      1986980.62     13884443.81      1987254.24     13884547.82
      1987381.84     13884509.42      1987449.22     13884328.11
      1987474.48     13884116.71
#Sta/Elev= 30
  4636.8 1486.89  4644.4 1487.00  4663.7 1484.46  4686.1 1483.60  4737.5 1473.83
  4756.7 1472.46  4769.6 1470.46  4808.6 1467.72  4840.2 1467.18  4857.0 1467.97
  4871.5 1467.82  4924.9 1464.86  5049.2 1466.14  5083.7 1466.72  5115.8 1465.96
  5166.3 1464.69  5223.9 1464.59  5229.8 1463.64  5230.1 1463.14  5233.8 1463.64
  5277.1 1465.42  5292.2 1467.41  5313.4 1468.69  5343.6 1468.44  5376.8 1469.74
  5394.9 1472.41  5409.8 1475.76  5440.3 1484.14  5455.4 1486.38  5469.1 1486.83
#Mann=7,-1,0
  4636.8    0.07       0  4769.6   0.035       0  4857.0    0.07       0
  5049.2     0.1       0  5115.8   0.035       0  5229.8    0.05       0
  5233.8   0.035       0
Bank Sta=5229.8,5233.8
Exp/Cntr=0.3,0.1

Chan Stop Cuts=-1