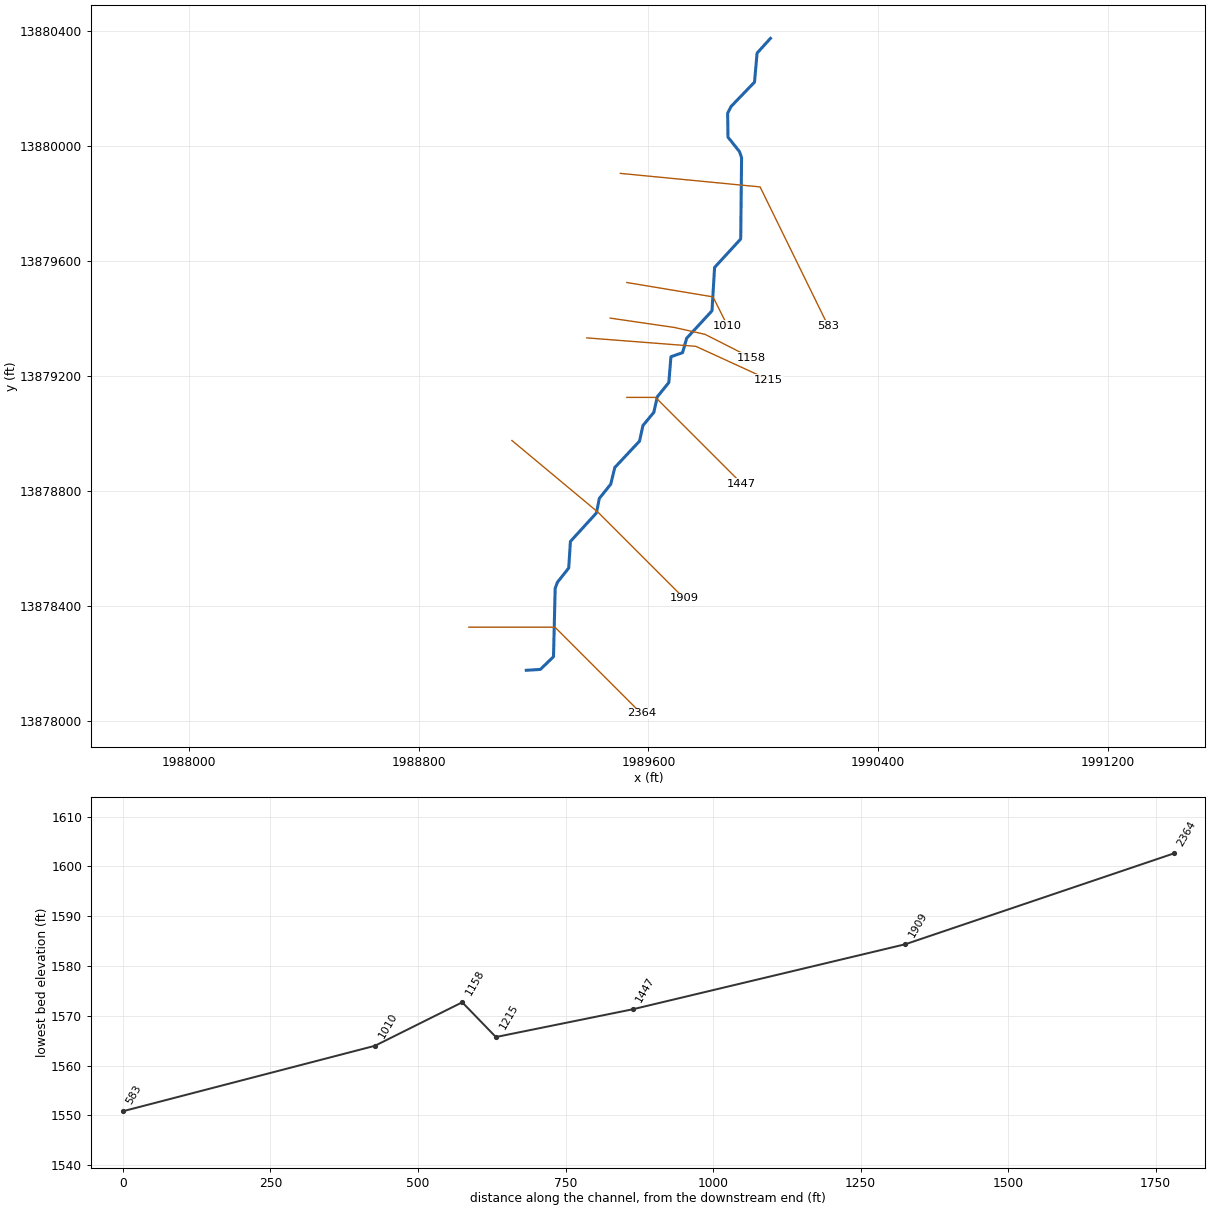
--- Stream0208.prj (project) ---

Proj Title=Stream0208 Base Level Engineering
Current Plan=p01
Default Exp/Contr=0.3,0.1
English Units
Geom File=g01
Flow File=f01
Plan File=p01
BEGIN DESCRIPTION:
Stream0208
END DESCRIPTION:

--- Stream0208.p01 (plan) ---

Plan Title=Multiple Run
Short Identifier=Multiple
Geom File=g01
Flow File=f01
Subcritical Flow
K Sum by GR= 0
Std Step Tol= 0.01
Critical Tol= 0.01
Num of Std Step Trials= 20
Max Error Tol= 0.3
Flow Tol Ratio= 0.001
Split Flow NTrial= 30
Split Flow Tol= 0.02
Split Flow Ratio= 0.02
Log Output Level= 0
Friction Slope Method= 1
Unsteady Friction Slope Method= 2
Unsteady Bridges Friction Slope Method= 1
Parabolic Critical Depth
Global Vel Dist=  1 , 1 , 1
Global Log Level= 0
CheckData=True
Encroach Param= -1, 0, 0, 0
BEGIN DESCRIPTION:
Multiple Run
END DESCRIPTION:

--- Stream0208.f01 (steady flow) ---

Flow Title=Multiple
Number of Profiles=7
Profile Names=10-year,25-year,50-year,1pct_min,100-year,1pct_plu,500-year
River Rch & RM= Stream0208,Reach-1,2364
     595     989    1358     908    1812    3616    3185
Boundary for River Rch & Prof#=Stream0208,Reach-1,1
Up Type=0
Dn Type=3
Dn Slope=0.005
Boundary for River Rch & Prof#=Stream0208,Reach-1,2
Up Type=0
Dn Type=3
Dn Slope=0.005
Boundary for River Rch & Prof#=Stream0208,Reach-1,3
Up Type=0
Dn Type=3
Dn Slope=0.005
Boundary for River Rch & Prof#=Stream0208,Reach-1,4
Up Type=0
Dn Type=3
Dn Slope=0.005
Boundary for River Rch & Prof#=Stream0208,Reach-1,5
Up Type=0
Dn Type=3
Dn Slope=0.005
Boundary for River Rch & Prof#=Stream0208,Reach-1,6
Up Type=0
Dn Type=3
Dn Slope=0.005
Boundary for River Rch & Prof#=Stream0208,Reach-1,7
Up Type=0
Dn Type=3
Dn Slope=0.005

--- Stream0208.g01 (geometry) ---

Geom Title=Existing Conditions

River Reach=Stream0208,Reach-1
Reach XY= 30
      1989175.00     13878175.00      1989224.02     13878178.12
      1989269.74     13878222.31      1989275.52     13878459.78
      1989283.14     13878481.06      1989322.64     13878530.98
      1989328.62     13878623.50      1989419.15     13878722.71
      1989429.19     13878773.27      1989468.90     13878822.81
      1989483.16     13878881.05      1989569.15     13878972.71
      1989581.10     13879027.19      1989618.92     13879072.80
      1989631.11     13879127.18      1989671.15     13879176.65
      1989678.49     13879266.52      1989718.95     13879280.80
      1989733.25     13879330.76      1989821.45     13879426.47
      1989830.48     13879577.44      1989921.45     13879676.47
      1989924.48     13879959.78      1989916.85     13879981.06
      1989877.16     13880030.98      1989875.94     13880114.52
      1989888.37     13880138.29      1989969.48     13880222.57
      1989978.39     13880323.59      1990025.00     13880375.00

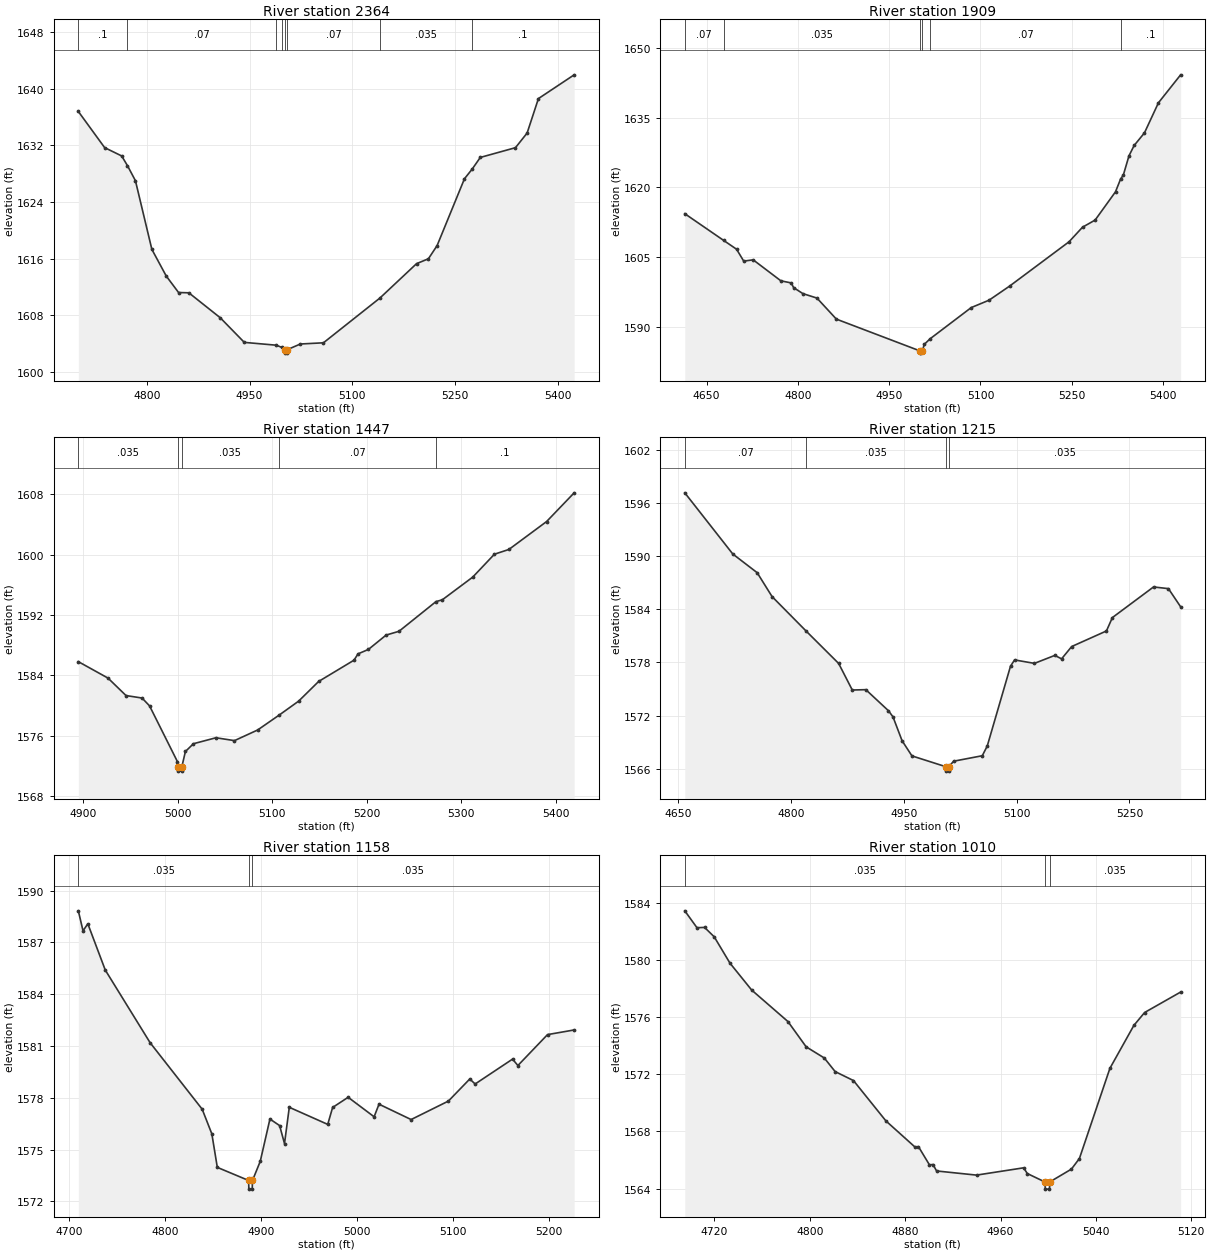
Type RM Length L Ch R = 1,2364,455,455,455
BEGIN DESCRIPTION:
Stream0208 4.0
END DESCRIPTION:
XS GIS Cut Line= 3
      1988975.03     13878325.00      1989275.00     13878325.00
      1989574.97     13878025.03
#Sta/Elev= 30
  4699.9 1636.80  4738.3 1631.69  4763.2 1630.51  4771.7 1629.13  4783.3 1627.01
  4807.3 1617.30  4828.3 1613.53  4846.3 1611.20  4861.3 1611.16  4907.2 1607.63
  4942.3 1604.15  4989.1 1603.75  4996.8 1603.45  5001.3 1603.13  5001.5 1602.63
  5005.0 1602.63  5005.3 1603.13  5024.2 1603.92  5057.9 1604.09  5140.4 1610.42
  5193.9 1615.28  5211.2 1615.97  5223.9 1617.83  5263.9 1627.29  5275.3 1628.67
  5287.0 1630.30  5338.4 1631.68  5355.4 1633.75  5371.9 1638.62  5424.1 1641.98
#Mann=8,-1,0
  4699.9     0.1       0  4771.7    0.07       0  4989.1   0.035       0
  4996.8    0.07       0  5001.3    0.05       0  5005.3    0.07       0
  5140.4   0.035       0  5275.3     0.1       0
Bank Sta=5001.3,5005.3
Exp/Cntr=0.3,0.1

Type RM Length L Ch R = 1,1909,462,462,462
BEGIN DESCRIPTION:
Stream0208 3.0
END DESCRIPTION:
XS GIS Cut Line= 3
      1989125.01     13878974.99      1989425.00     13878725.00
      1989725.03     13878424.97
#Sta/Elev= 30
  4614.1 1614.35  4677.8 1608.62  4699.2 1606.71  4710.9 1604.16  4726.5 1604.43
  4772.0 1599.92  4789.0 1599.47  4792.9 1598.46  4808.2 1597.17  4831.3 1596.21
  4863.2 1591.69  5000.1 1584.88  5000.3 1584.38  5004.1 1584.88  5008.0 1586.31
  5017.2 1587.46  5084.8 1594.17  5114.1 1595.76  5148.0 1598.80  5245.6 1608.32
  5267.7 1611.45  5288.4 1612.98  5321.9 1619.06  5330.3 1621.82  5334.7 1622.63
  5344.0 1626.78  5352.5 1629.01  5369.5 1631.73  5392.4 1638.18  5428.9 1644.20
#Mann=6,-1,0
  4614.1    0.07       0  4677.8   0.035       0  5000.1   0.035       0
  5004.1   0.035       0  5017.2    0.07       0  5330.3     0.1       0
Bank Sta=5000.1,5004.1
Exp/Cntr=0.3,0.1

Type RM Length L Ch R = 1,1447,232,232,232
BEGIN DESCRIPTION:
Stream0208 2.0
END DESCRIPTION:
XS GIS Cut Line= 3
      1989525.04     13879125.00      1989625.00     13879125.00
      1989924.99     13878825.01
#Sta/Elev= 30
  4895.0 1585.81  4926.4 1583.63  4945.4 1581.32  4962.4 1580.99  4970.3 1579.95
  4999.8 1572.56  5000.3 1571.81  5000.6 1571.31  5004.1 1571.31  5004.3 1571.81
  5008.2 1573.91  5016.7 1574.94  5040.5 1575.73  5060.1 1575.35  5084.6 1576.76
  5107.3 1578.73  5127.9 1580.58  5149.1 1583.19  5186.4 1586.00  5190.7 1586.84
  5201.7 1587.43  5220.4 1589.33  5234.0 1589.83  5273.1 1593.76  5279.8 1594.00
  5312.0 1597.01  5334.9 1600.04  5350.2 1600.67  5390.1 1604.37  5419.2 1608.17
#Mann=5,-1,0
  4895.0   0.035       0  5000.3   0.035       0  5004.3   0.035       0
  5107.3    0.07       0  5273.1     0.1       0
Bank Sta=5000.3,5004.3
Exp/Cntr=0.3,0.1

Type RM Length L Ch R = 1,1215,57,57,57
BEGIN DESCRIPTION:
Mapping XS c7fdefac
END DESCRIPTION:
XS GIS Cut Line= 3
      1989385.50     13879332.21      1989765.29     13879302.79
      1990018.08     13879186.95
#Sta/Elev= 30
  4659.0 1597.16  4722.8 1590.25  4755.2 1588.14  4775.0 1585.44  4820.6 1581.52
  4863.5 1577.89  4881.6 1574.89  4899.6 1574.93  4929.7 1572.55  4935.7 1571.86
  4947.8 1569.16  4960.9 1567.45  5005.9 1566.23  5006.2 1565.73  5009.7 1565.73
  5009.9 1566.23  5016.3 1566.85  5054.4 1567.47  5061.0 1568.57  5091.9 1577.58
  5097.3 1578.29  5123.7 1577.90  5150.8 1578.80  5159.8 1578.41  5173.2 1579.80
  5219.4 1581.56  5227.3 1583.07  5282.0 1586.53  5301.8 1586.34  5318.0 1584.29
#Mann=4,-1,0
  4659.0    0.07       0  4820.6   0.035       0  5005.9   0.035       0
  5009.9   0.035       0
Bank Sta=5005.9,5009.9
Exp/Cntr=0.3,0.1

Type RM Length L Ch R = 1,1158,148,148,148
BEGIN DESCRIPTION:
Stream0208 D
END DESCRIPTION:
XS GIS Cut Line= 4
      1989467.18     13879401.00      1989690.73     13879368.44
      1989797.07     13879344.57      1989959.79     13879262.13
#Sta/Elev= 30
  4709.3 1588.83  4714.2 1587.67  4719.2 1588.08  4737.4 1585.40  4784.2 1581.19
  4838.5 1577.34  4848.6 1575.91  4854.3 1573.97  4887.0 1573.21  4887.2 1572.71
  4890.7 1572.71  4891.0 1573.21  4899.1 1574.32  4909.2 1576.77  4919.3 1576.39
  4924.4 1575.35  4929.4 1577.45  4969.5 1576.46  4974.6 1577.44  4990.8 1578.03
  5017.9 1576.90  5023.0 1577.63  5056.5 1576.74  5095.4 1577.81  5117.7 1579.09
  5123.3 1578.80  5162.3 1580.24  5167.9 1579.87  5198.8 1581.66  5226.6 1581.93
#Mann=3,-1,0
  4709.3   0.035       0  4887.0   0.035       0  4891.0   0.035       0
Bank Sta=4887,4891
Exp/Cntr=0.3,0.1

Type RM Length L Ch R = 1,1010,427,427,427
BEGIN DESCRIPTION:
Stream0208 1.0
END DESCRIPTION:
XS GIS Cut Line= 3
      1989525.03     13879524.99      1989825.00     13879475.00
      1989875.00     13879375.01
#Sta/Elev= 30
  4695.1 1583.43  4705.3 1582.25  4711.7 1582.27  4719.8 1581.61  4733.0 1579.77
  4751.2 1577.89  4781.6 1575.69  4796.9 1573.92  4812.1 1573.14  4821.2 1572.19
  4836.6 1571.56  4863.8 1568.74  4888.1 1566.92  4891.1 1566.94  4900.3 1565.67
  4903.3 1565.69  4906.3 1565.24  4939.8 1564.95  4979.3 1565.46  4982.4 1565.06
  4997.2 1564.47  4997.5 1563.97  5001.0 1563.97  5001.2 1564.47  5019.4 1565.37
  5026.1 1566.11  5051.7 1572.42  5071.8 1575.42  5080.8 1576.32  5111.0 1577.75
#Mann=3,-1,0
  4695.1   0.035       0  4997.2   0.035       0  5001.2   0.035       0
Bank Sta=4997.2,5001.2
Exp/Cntr=0.3,0.1

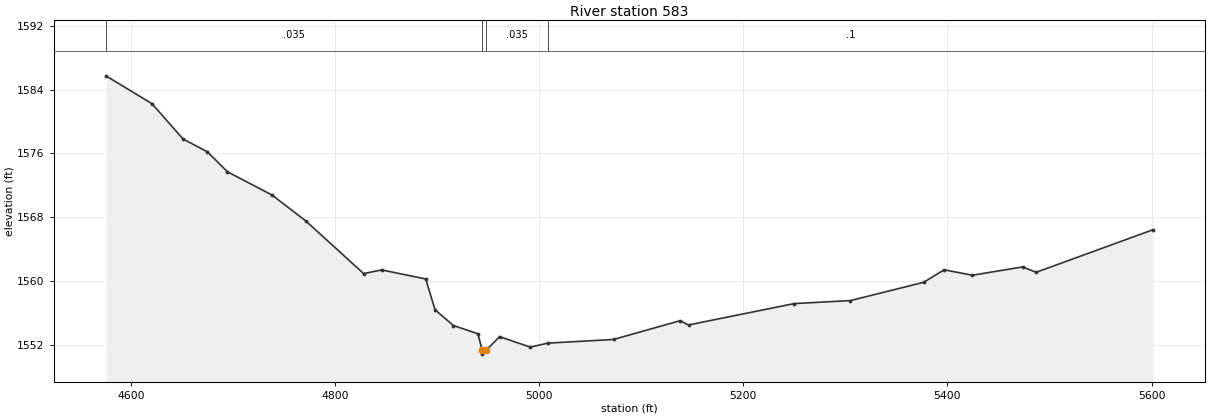
Type RM Length L Ch R = 1,583,0,0,0
BEGIN DESCRIPTION:
Stream0208 0.0
END DESCRIPTION:
XS GIS Cut Line= 3
      1989502.45     13879904.86      1989988.93     13879857.74
      1990225.24     13879375.14
#Sta/Elev= 30
  4575.4 1585.74  4620.6 1582.24  4651.1 1577.80  4674.8 1576.21  4694.5 1573.70
  4738.1 1570.79  4771.3 1567.53  4828.0 1560.92  4845.5 1561.39  4888.8 1560.25
  4897.9 1556.39  4915.9 1554.41  4940.0 1553.37  4944.1 1551.32  4944.3 1550.82
  4948.1 1551.32  4961.1 1553.01  4991.3 1551.70  5008.5 1552.20  5072.8 1552.66
  5138.0 1555.01  5146.3 1554.48  5249.8 1557.16  5305.0 1557.54  5376.7 1559.83
  5396.8 1561.40  5424.5 1560.72  5473.6 1561.76  5487.0 1561.09  5601.5 1566.43
#Mann=4,-1,0
  4575.4   0.035       0  4944.1   0.035       0  4948.1   0.035       0
  5008.5     0.1       0
Bank Sta=4944.1,4948.1
Exp/Cntr=0.3,0.1

Chan Stop Cuts=-1